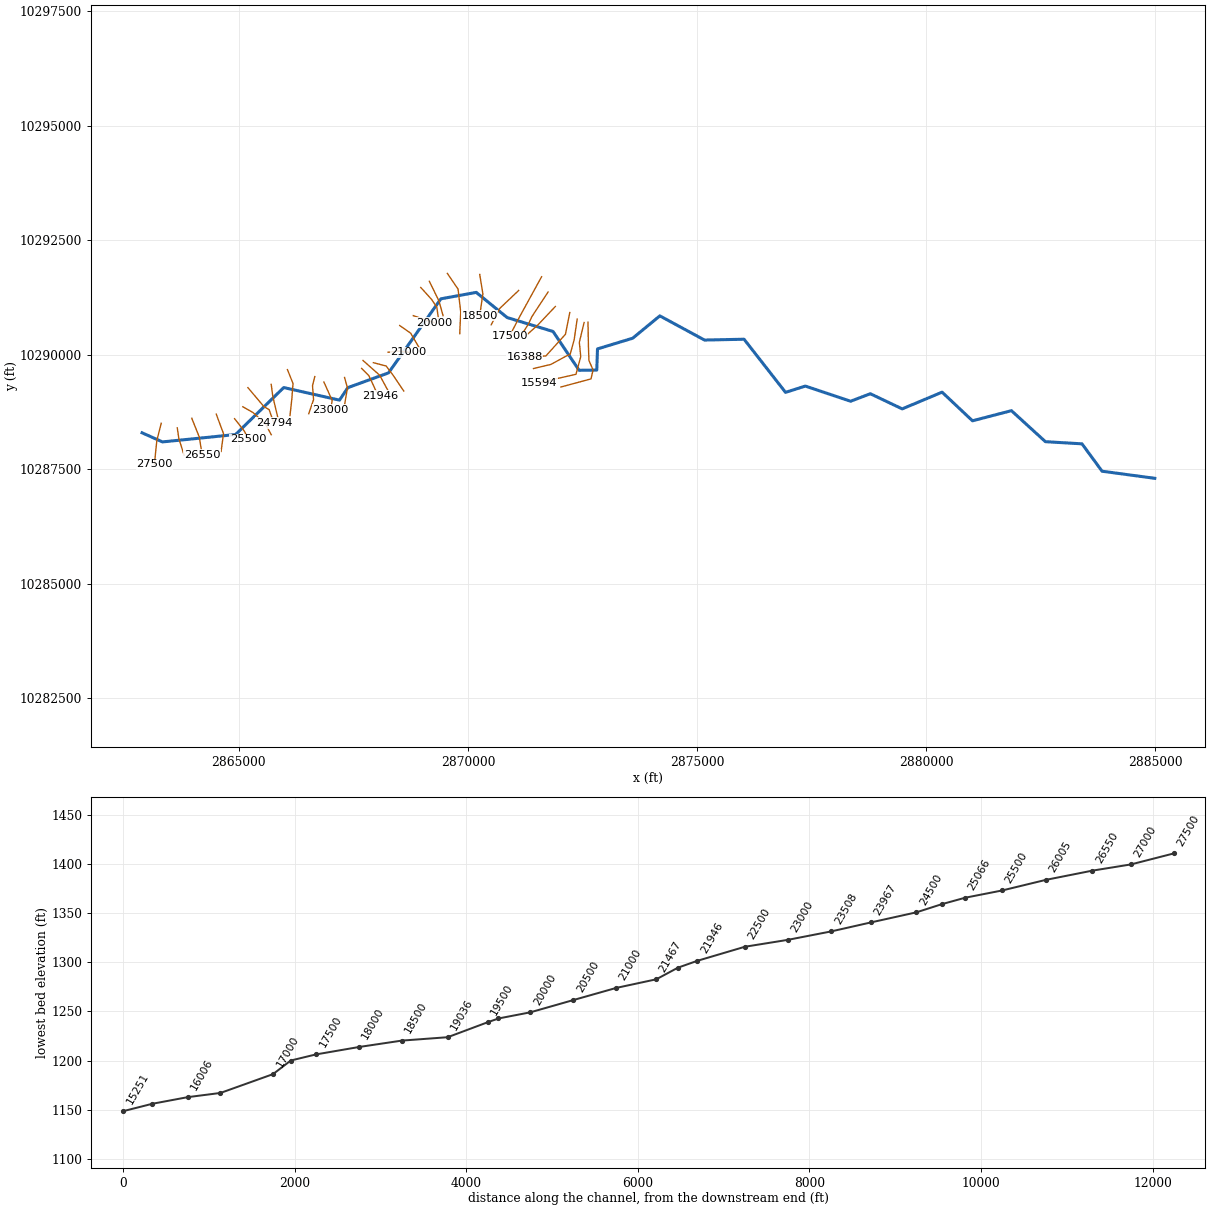
--- CALVERT CREEK.prj (project) ---

Proj Title=CALVERT CREEK Base Level Engineering
Current Plan=p01
Default Exp/Contr=0.3,0.1
English Units
Geom File=g01
Flow File=f01
Plan File=p01
Y Axis Title=Elevation
X Axis Title(PF)=Main Channel Distance
X Axis Title(XS)=Station
BEGIN DESCRIPTION:
CALVERT CREEK
END DESCRIPTION:
DSS Export Rating Curves= 0
DSS Export Rating Curve Sorted= 0
DSS Export Volume Flow Curves= 0
DXF OffsetX= 0
DXF OffsetY= 0
DXF ScaleX= 1
DXF ScaleY= 10

--- CALVERT CREEK.p01 (plan) ---

Plan Title=Multiple Run
Short Identifier=Multiple
Geom File=g01
Flow File=f01
Subcritical Flow
K Sum by GR= 0
Std Step Tol= 0.01
Critical Tol= 0.01
Num of Std Step Trials= 20
Max Error Tol= 0.3
Flow Tol Ratio= 0.001
Split Flow NTrial= 30
Split Flow Tol= 0.02
Split Flow Ratio= 0.02
Log Output Level= 0
Friction Slope Method= 1
Unsteady Friction Slope Method= 2
Unsteady Bridges Friction Slope Method= 1
Parabolic Critical Depth
Global Vel Dist=  1 , 1 , 1
Global Log Level= 0
CheckData=True
Encroach Param= -1, 0, 0, 0
BEGIN DESCRIPTION:
Multiple Run
END DESCRIPTION:

--- CALVERT CREEK.f01 (steady flow) ---

Flow Title=Multiple
Number of Profiles=7
Profile Names=10-year,25-year,50-year,1pct_min,100-year,1pct_plu,500-year
River Rch & RM= CALVERT CREEK,Reach-1,27500
     419     673    1150     927    1572    2666    2214
River Rch & RM= CALVERT CREEK,Reach-1,20500
     836    1421    2653    1918    3770    7412    5417
River Rch & RM= CALVERT CREEK,Reach-1,9500
    1144    1987    3773    2661    5426   11063    7792
Boundary for River Rch & Prof#=CALVERT CREEK,Reach-1,1
Up Type=0
Dn Type=3
Dn Slope=0.005
Boundary for River Rch & Prof#=CALVERT CREEK,Reach-1,2
Up Type=0
Dn Type=3
Dn Slope=0.005
Boundary for River Rch & Prof#=CALVERT CREEK,Reach-1,3
Up Type=0
Dn Type=3
Dn Slope=0.005
Boundary for River Rch & Prof#=CALVERT CREEK,Reach-1,4
Up Type=0
Dn Type=3
Dn Slope=0.005
Boundary for River Rch & Prof#=CALVERT CREEK,Reach-1,5
Up Type=0
Dn Type=3
Dn Slope=0.005
Boundary for River Rch & Prof#=CALVERT CREEK,Reach-1,6
Up Type=0
Dn Type=3
Dn Slope=0.005
Boundary for River Rch & Prof#=CALVERT CREEK,Reach-1,7
Up Type=0
Dn Type=3
Dn Slope=0.005

--- CALVERT CREEK.g01 (geometry) ---

Geom Title=Existing Conditions
Program Version=4.00

River Reach=CALVERT CREEK   ,Reach-1
Reach XY= 30
      2862887.25       10288295.      2863332.75       10288096.
      2864927.75       10288257.      2865978.75       10289283.
       2867196.5       10289008.        2867378.       10289281.
      2868265.25       10289603.       2869407.5       10291220.
       2870179.5       10291361.       2870854.5       10290811.
       2871854.5       10290508.        2872423.       10289660.
      2872809.75       10289664.      2872825.25       10290127.
      2873593.25       10290360.      2874185.75       10290848.
      2875160.75       10290320.      2876023.25       10290338.
       2876928.5       10289178.      2877360.75       10289315.
      2878348.75       10288984.      2878778.25       10289148.
      2879474.25       10288817.        2880345.       10289182.
      2881007.75       10288557.      2881857.75       10288778.
      2882599.25       10288101.      2883397.25       10288054.
      2883835.75       10287456.      2884985.75       10287301.

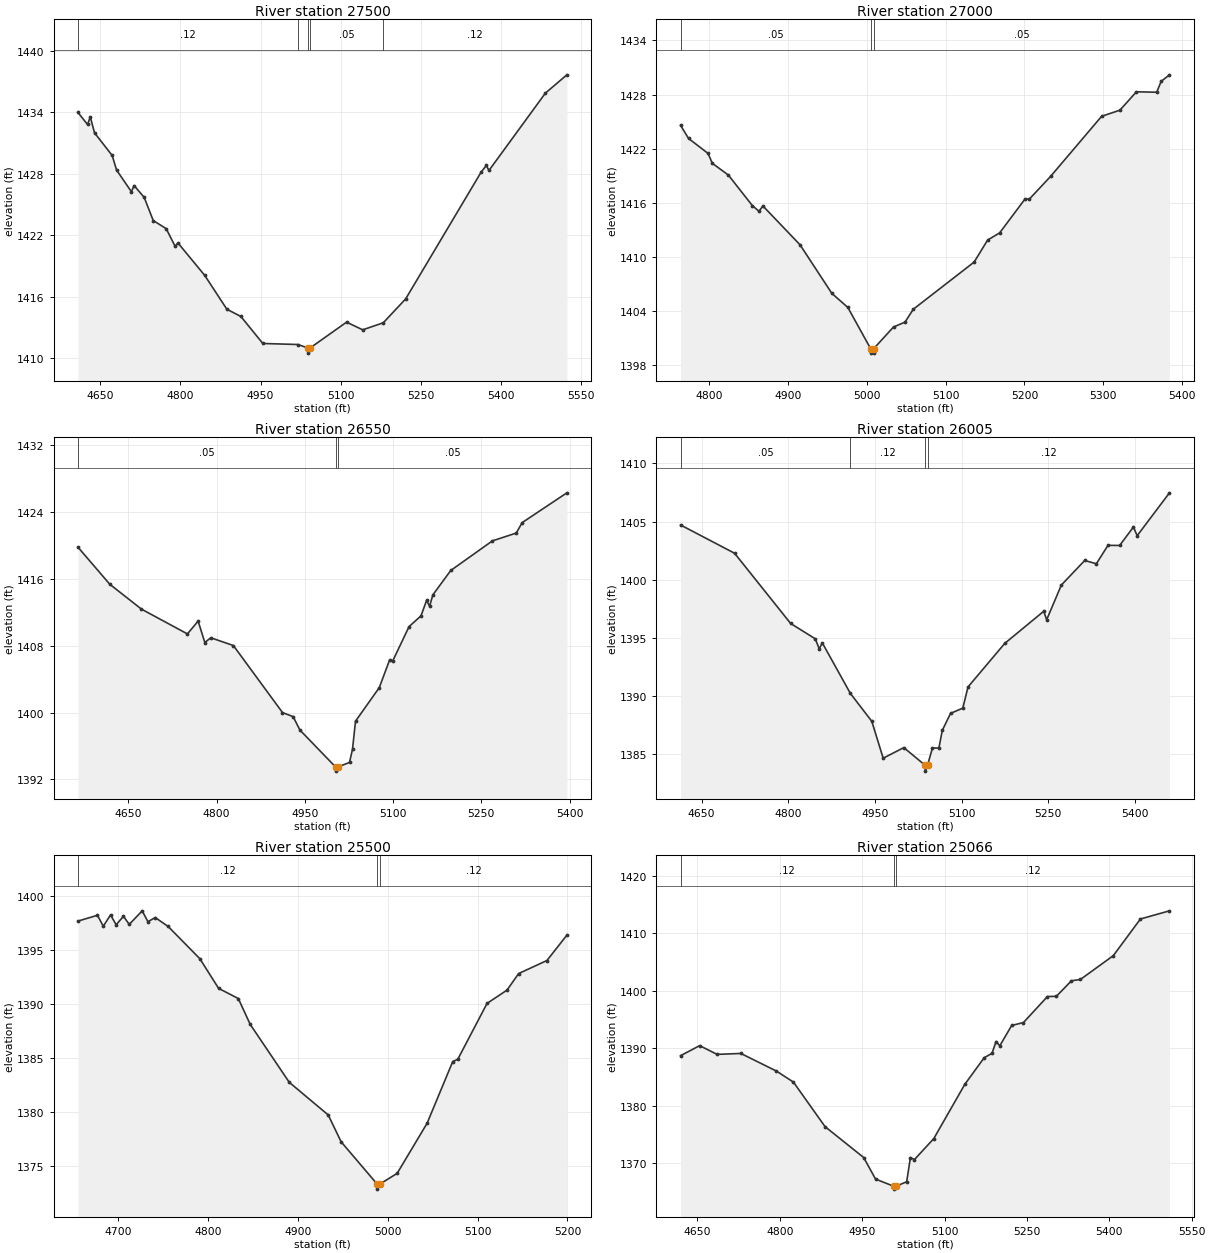
Type RM Length L Ch R = 1 ,27500   ,500,500,500
BEGIN DESCRIPTION:
CALVERT CREEK 55.0
END DESCRIPTION:
XS GIS Cut Line= 3
      2863305.68     10288503.08       2863209.5     10288123.47
      2863155.69     10287603.15
#Sta/Elev= 30
  4608.4 1433.96  4626.3 1432.79  4631.4 1433.53  4639.3 1431.98  4672.4 1429.77
  4680.6 1428.35  4708.3 1426.24  4713.4 1426.84  4732.2 1425.69  4749.2 1423.43
  4773.4 1422.64  4790.2 1420.91  4795.4 1421.25  4845.6 1418.08  4886.9 1414.79
  4913.2 1414.08  4954.2 1411.45  5019.9 1411.35  5038.6 1411.01  5038.8 1410.51
  5042.6 1411.01  5110.9 1413.53  5141.1 1412.78  5179.6 1413.47  5221.5  1415.8
  5362.3 1428.12  5372.3  1428.8  5377.3 1428.31  5482.9 1435.85  5523.1 1437.63
#Mann= 5 ,-1 , 0
  4608.4     .12       0  5019.9     .05       0  5038.6     .07       0
  5042.6     .05       0  5179.6     .12       0
Bank Sta=5038.6,5042.6
XS Rating Curve= 0 ,0
Exp/Cntr=0.3,0.1

Type RM Length L Ch R = 1 ,27000   ,450,450,450
BEGIN DESCRIPTION:
CALVERT CREEK 54.0
END DESCRIPTION:
XS GIS Cut Line= 3
      2863655.69      10288403.1      2863690.12     10288169.32
      2863805.68     10287803.12
#Sta/Elev= 30
  4763.7 1424.59  4773.8 1423.14  4798.5 1421.48  4804.1 1420.37  4824.3 1419.08
  4854.7  1415.7  4863.2 1415.06  4868.2 1415.65  4915.3 1411.34  4955.7 1405.95
  4975.9  1404.4  5004.8 1399.83  5005.1 1399.33  5008.6 1399.33  5008.8 1399.83
  5033.9 1402.23  5048.5 1402.77  5058.9 1404.19  5136.2 1409.43  5153.3 1411.87
  5168.5 1412.66  5200.9 1416.44  5206.1  1416.4  5233.2 1418.93  5297.9 1425.59
  5321.1 1426.27  5342.1 1428.31  5367.8 1428.26  5373.5 1429.47    5384 1430.19
#Mann= 3 ,-1 , 0
  4763.7     .05       0  5004.8     .05       0  5008.8     .05       0
Bank Sta=5004.8,5008.8
XS Rating Curve= 0 ,0
Exp/Cntr=0.3,0.1

Type RM Length L Ch R = 1 ,26550   ,545,545,545
BEGIN DESCRIPTION:
Mapping XS 5af581d5
END DESCRIPTION:
XS GIS Cut Line= 3
      2863972.34     10288612.69      2864137.22      10288200.5
      2864196.57     10287818.02
#Sta/Elev= 30
  4564.4 1419.76  4618.5 1415.33  4672.3 1412.36  4750.4  1409.4  4768.6 1410.93
    4780 1408.37  4790.1 1408.94  4828.5 1408.01    4912    1400  4930.1 1399.51
  4941.6 1397.91  5002.2  1393.5  5002.5    1393  5006.2  1393.5  5025.9 1394.04
    5031 1395.62  5036.1 1398.97  5076.5 1402.98  5093.9 1406.26    5099 1406.12
  5127.1 1410.27  5147.4 1411.56  5156.9  1413.4    5162 1412.72  5167.6 1414.07
    5198 1416.98  5268.8 1420.52  5309.3 1421.45  5319.4  1422.7  5395.4 1426.26
#Mann= 3 ,-1 , 0
  4564.4     .05       0  5002.2     .05       0  5006.2     .05       0
Bank Sta=5002.2,5006.2
XS Rating Curve= 0 ,0
Exp/Cntr=0.3,0.1

Type RM Length L Ch R = 1 ,26005   ,505,505,505
BEGIN DESCRIPTION:
Mapping XS d0731acd
END DESCRIPTION:
XS GIS Cut Line= 3
      2864506.53     10288701.67       2864664.8     10288276.34
       2864612.1     10287887.72
#Sta/Elev= 30
  4613.6 1404.71  4707.1 1402.28  4804.1 1396.25  4846.8 1394.93  4853.5 1394.07
  4858.9 1394.58  4907.5 1390.24  4944.5 1387.85  4964.2 1384.68  4999.9 1385.59
  5036.9 1384.07  5037.1 1383.57  5040.9 1384.07  5049.5 1385.56  5060.6 1385.55
  5066.5 1387.07  5080.8 1388.53    5102 1388.98    5111  1390.8  5174.6 1394.54
    5242  1397.3  5247.1 1396.57  5272.5 1399.55  5312.9 1401.66  5333.1 1401.38
  5353.2 1402.96  5373.4 1402.95  5397.2 1404.53  5403.7 1403.79  5459.6 1407.47
#Mann= 4 ,-1 , 0
  4613.6     .05       0  4907.5     .12       0  5036.9     .07       0
  5040.9     .12       0
Bank Sta=5036.9,5040.9
XS Rating Curve= 0 ,0
Exp/Cntr=0.3,0.1

Type RM Length L Ch R = 1 ,25500   ,434,434,434
BEGIN DESCRIPTION:
CALVERT CREEK 51.0
END DESCRIPTION:
XS GIS Cut Line= 3
      2864905.65     10288603.15      2865118.79     10288332.62
      2865205.67     10288153.14
#Sta/Elev= 30
  4655.6  1397.7  4677.3 1398.24  4683.7 1397.22  4691.8 1398.27  4698.1 1397.36
  4706.2 1398.15  4712.6 1397.39    4727 1398.65  4733.4 1397.64  4741.5 1398.03
  4755.9  1397.2  4791.2 1394.21    4812 1391.47  4833.9 1390.53  4847.2 1388.13
  4890.6 1382.77  4933.9 1379.75  4948.3 1377.26    4988 1373.38  4988.2 1372.88
    4992 1373.38  5010.6 1374.34  5043.9 1378.98  5072.4 1384.69    5078  1384.9
  5110.6 1390.08  5132.8 1391.31  5145.7 1392.84  5177.2 1394.05  5199.4  1396.4
#Mann= 3 ,-1 , 0
  4655.6     .12       0    4988     .07       0    4992     .12       0
Bank Sta=4988,4992
XS Rating Curve= 0 ,0
Exp/Cntr=0.3,0.1

Type RM Length L Ch R = 1 ,25066   ,272,272,272
BEGIN DESCRIPTION:
Mapping XS e7a88bb7
END DESCRIPTION:
XS GIS Cut Line= 4
      2865086.89     10288863.25      2865307.78     10288737.97
      2865578.17     10288490.67      2865706.78     10288253.23
#Sta/Elev= 30
  4619.2 1388.67    4654 1390.42  4685.7  1388.9    4729 1389.06  4793.9 1385.99
  4824.7 1384.08  4882.4 1376.32  4952.7 1370.95  4974.3  1367.2  5007.4 1365.95
  5007.7 1365.45  5011.4 1365.95    5031 1366.73  5037.8 1370.94  5045.2  1370.6
  5080.4 1374.25  5137.1 1383.72  5172.2 1388.32  5186.4 1389.08  5193.8 1391.14
  5200.6 1390.39  5222.2 1393.93  5243.7 1394.44  5287.4 1398.97  5303.6    1399
  5331.1 1401.71  5347.3 1401.93  5407.3 1406.08  5456.7 1412.46  5509.6 1413.88
#Mann= 3 ,-1 , 0
  4619.2     .12       0  5007.4     .07       0  5011.4     .12       0
Bank Sta=5007.4,5011.4
XS Rating Curve= 0 ,0
Exp/Cntr=0.3,0.1

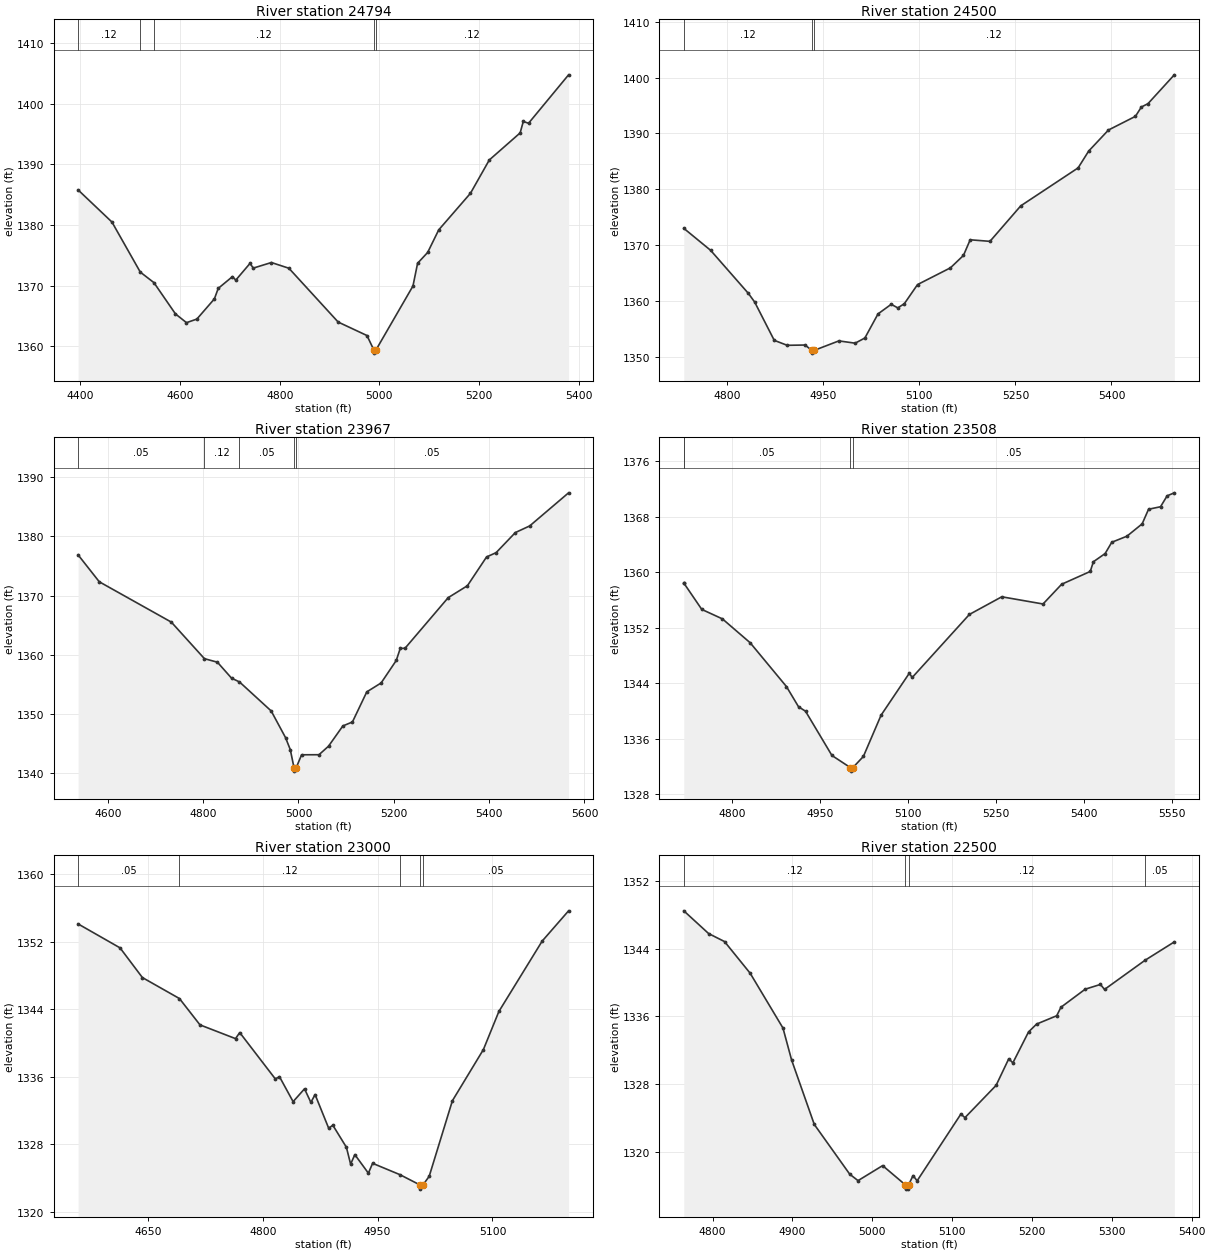
Type RM Length L Ch R = 1 ,24794   ,294,294,294
BEGIN DESCRIPTION:
Mapping XS dc04144b
END DESCRIPTION:
XS GIS Cut Line= 4
      2865197.63     10289281.08      2865548.35     10288864.38
      2865659.46     10288801.88      2865763.39     10288507.41
#Sta/Elev= 30
  4395.2  1385.8  4463.2  1380.5  4520.1 1372.25  4547.4 1370.52  4590.7 1365.36
  4612.8 1363.92  4633.6 1364.51  4668.8 1367.84  4676.5 1369.57  4705.1 1371.51
  4711.7 1370.93  4740.3 1373.69  4746.8 1372.91  4783.2 1373.83  4818.3 1372.89
  4917.2 1364.02    4975  1361.8  4988.9  1359.4  4989.2  1358.9  4992.9  1359.4
  5067.3 1369.96  5076.6 1373.71  5096.8 1375.49    5119 1379.21  5182.7 1385.24
  5220.5 1390.73  5282.4 1395.19  5288.7 1397.07  5299.3 1396.78  5379.6 1404.76
#Mann= 5 ,-1 , 0
  4395.2     .12       0  4520.1     .05       0  4547.4     .12       0
  4988.9     .07       0  4992.9     .12       0
#XS Ineff= 2 , 0
       0    4783                       0
Permanent Ineff=
       F       F
Bank Sta=4988.9,4992.9
XS Rating Curve= 0 ,0
Exp/Cntr=0.3,0.1

Type RM Length L Ch R = 1 ,24500   ,533,533,533
BEGIN DESCRIPTION:
CALVERT CREEK 49.0
END DESCRIPTION:
XS GIS Cut Line= 3
      2865705.68     10289353.11       2865740.5     10289087.68
      2865855.69     10288603.08
#Sta/Elev= 30
  4732.3    1373  4774.2 1369.06  4833.2 1361.34  4842.9 1359.81  4873.5 1352.95
  4893.7 1352.06  4921.7 1352.11    4932 1351.16  4932.3 1350.66    4936 1351.16
  4974.4 1352.85  4999.8 1352.44    5015 1353.37  5035.5 1357.68  5056.1  1359.4
  5066.4 1358.76  5076.6 1359.51  5097.2 1362.93  5148.6 1365.93  5168.9 1368.15
  5179.4 1370.95  5210.3 1370.67  5258.4 1377.03  5347.9 1383.82  5364.4 1386.83
  5395.3  1390.6  5437.4 1393.05  5446.7 1394.72    5457 1395.32  5498.1 1400.48
#Mann= 3 ,-1 , 0
  4732.3     .12       0    4932     .07       0    4936     .12       0
Bank Sta=4932,4936
XS Rating Curve= 0 ,0
Exp/Cntr=0.3,0.1

Type RM Length L Ch R = 1 ,23967   ,459,459,459
BEGIN DESCRIPTION:
Mapping XS 4b43085b
END DESCRIPTION:
XS GIS Cut Line= 4
      2866059.58     10289674.43      2866181.58     10289371.06
       2866155.2     10289031.44      2866115.64     10288672.04
#Sta/Elev= 30
  4537.5 1376.87    4582 1372.32  4733.2 1365.51  4802.6 1359.34  4829.9 1358.74
  4859.5 1356.05  4876.2 1355.41  4942.7 1350.51  4972.8 1346.01  4982.8 1343.98
  4990.8 1340.85  4991.1 1340.35  4994.8 1340.85  5006.5 1343.11    5043 1343.12
    5063 1344.56  5093.1 1347.98  5113.2 1348.65  5143.3 1353.73  5173.4 1355.24
  5205.1 1359.03  5213.5 1361.06  5223.6  1361.1  5314.1 1369.64  5354.4 1371.65
  5394.6 1376.51  5414.7 1377.24    5455 1380.63  5485.1 1381.75  5566.7 1387.34
#Mann= 5 ,-1 , 0
  4537.5     .05       0  4802.6     .12       0  4876.2     .05       0
  4990.8     .05       0  4994.8     .05       0
Bank Sta=4990.8,4994.8
XS Rating Curve= 0 ,0
Exp/Cntr=0.3,0.1

Type RM Length L Ch R = 1 ,23508   ,508,508,508
BEGIN DESCRIPTION:
Mapping XS 7b894895
END DESCRIPTION:
XS GIS Cut Line= 4
      2866656.41     10289522.78      2866606.94      10289324.9
      2866630.02     10289018.25      2866524.51     10288711.59
#Sta/Elev= 30
  4718.1 1358.41  4718.4 1358.41  4748.7 1354.64  4783.9 1353.27  4831.1 1349.83
    4893  1343.5  4913.6 1340.58  4925.5 1339.94  4970.5 1333.55  5002.1 1331.79
  5002.3 1331.29  5006.1 1331.79  5024.1 1333.41  5054.2 1339.36  5102.3 1345.42
  5107.3 1344.81  5204.7 1353.91  5259.9 1356.46  5330.2 1355.42  5361.9 1358.27
  5410.7 1360.12    5416 1361.52    5436  1362.7  5447.3 1364.33  5473.2 1365.21
  5499.1 1366.99    5510  1369.1  5530.4 1369.46  5541.7 1371.04  5553.9 1371.47
#Mann= 4 ,-1 , 0
  4718.1     .12       0  4718.4     .05       0  5002.1     .03       0
  5006.1     .05       0
Bank Sta=5002.1,5006.1
XS Rating Curve= 0 ,0
Exp/Cntr=0.3,0.1

Type RM Length L Ch R = 1 ,23000   ,500,500,500
BEGIN DESCRIPTION:
CALVERT CREEK 46.0
END DESCRIPTION:
XS GIS Cut Line= 3
      2866855.67     10289403.13      2867035.38      10289000.3
      2867005.69     10288803.13
#Sta/Elev= 30
  4558.9  1354.1  4613.7 1351.26  4642.9 1347.74  4691.3 1345.25  4718.1 1342.13
  4764.5  1340.5    4770 1341.22  4816.5 1335.72  4821.9 1335.99  4839.7 1333.03
  4854.6 1334.55  4862.9 1332.94  4868.4 1333.87  4886.1 1329.89  4891.6 1330.23
  4909.3 1327.62  4914.8 1325.62  4920.3 1326.75    4938 1324.55  4943.5 1325.72
  4979.3 1324.37  5005.3 1323.16  5005.5 1322.66  5009.3 1323.16  5017.4 1324.18
  5047.7 1333.14  5088.2 1339.21  5108.4 1343.72  5164.9 1352.06  5199.4 1355.65
#Mann= 5 ,-1 , 0
  4558.9     .05       0  4691.3     .12       0  4979.3     .05       0
  5005.3     .05       0  5009.3     .05       0
Bank Sta=5005.3,5009.3
XS Rating Curve= 0 ,0
Exp/Cntr=0.3,0.1

Type RM Length L Ch R = 1 ,22500   ,554,554,554
BEGIN DESCRIPTION:
CALVERT CREEK 45.0
END DESCRIPTION:
XS GIS Cut Line= 3
      2867305.69     10289503.08      2867369.77     10289275.95
      2867305.68     10288903.11
#Sta/Elev= 30
    4764 1348.44  4795.1 1345.76    4815 1344.82  4847.1 1341.09  4888.2 1334.63
    4899 1330.87  4927.4 1323.28  4971.8 1317.42  4982.2 1316.66    5013 1318.43
  5041.5 1316.16  5041.7 1315.66  5045.2 1315.66  5045.5 1316.16  5051.1 1317.26
  5056.2 1316.64    5111  1324.5  5116.1 1324.08  5155.1 1327.88    5171 1331.02
  5176.1 1330.53  5195.7 1334.17  5205.8  1335.1    5231 1336.08  5236.3 1337.08
  5266.7 1339.21  5285.8 1339.77  5290.9 1339.18  5341.7 1342.62  5378.3 1344.78
#Mann= 4 ,-1 , 0
    4764     .12       0  5041.5     .07       0  5045.5     .12       0
  5341.7     .05       0
Bank Sta=5041.5,5045.5
XS Rating Curve= 0 ,0
Exp/Cntr=0.3,0.1

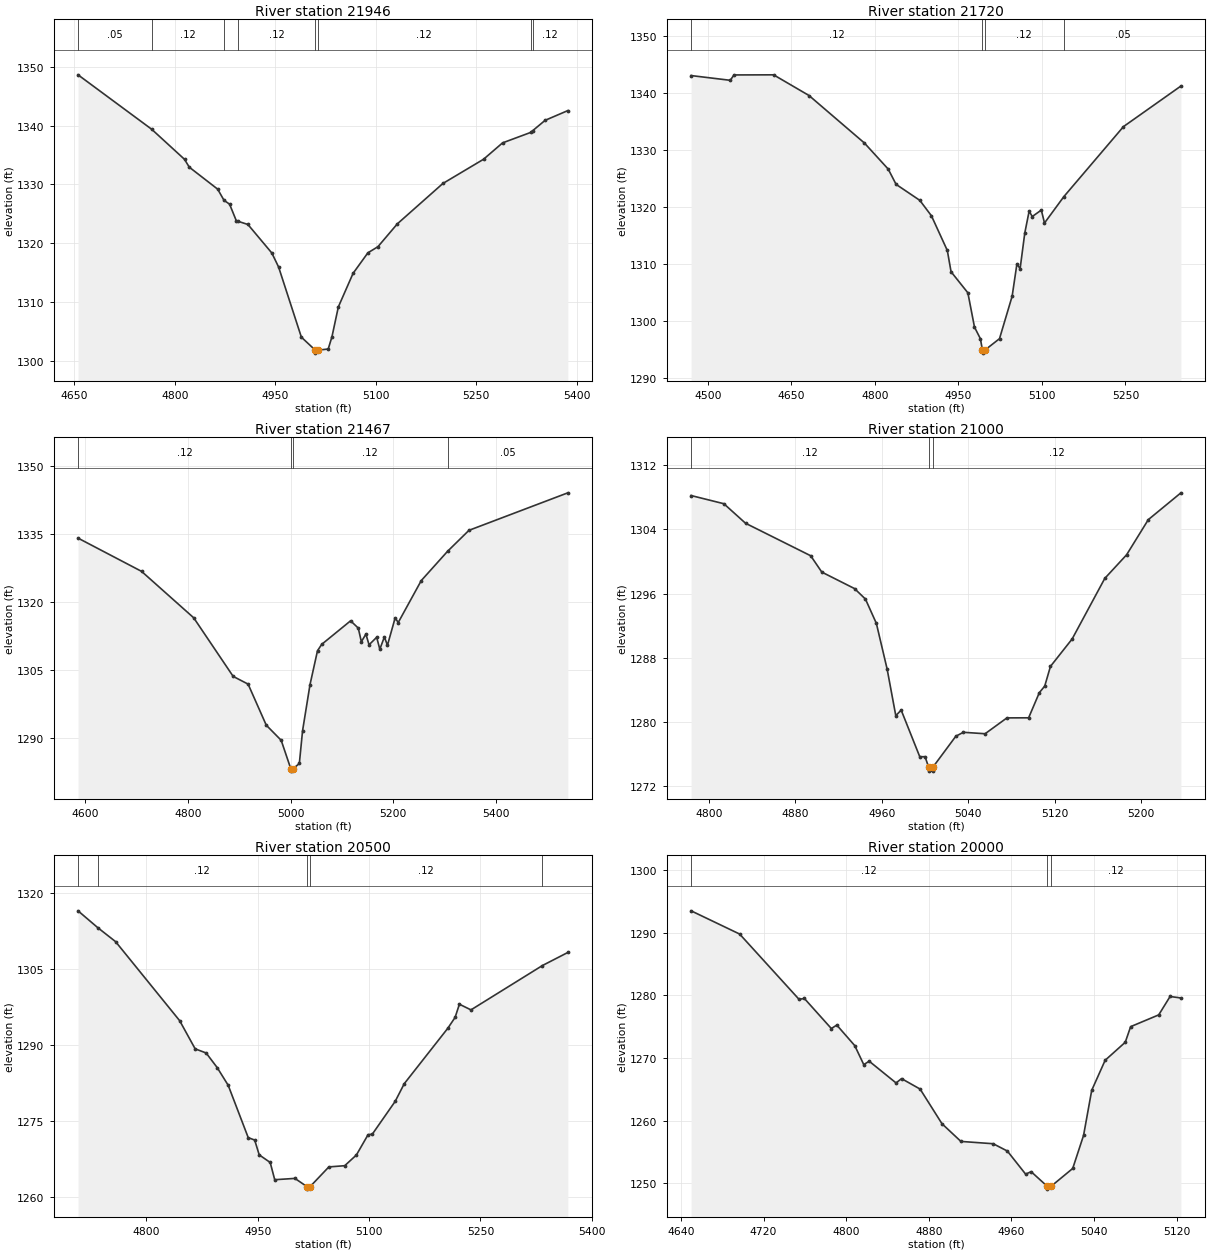
Type RM Length L Ch R = 1 ,21946   ,226,226,226
BEGIN DESCRIPTION:
Mapping XS 3ee3a9d6
END DESCRIPTION:
XS GIS Cut Line= 4
      2867678.56     10289700.82      2867836.86     10289542.53
      2867991.83     10289209.49      2868084.16     10289103.98
#Sta/Elev= 30
  4655.6 1348.61  4765.5 1339.38  4814.6 1334.27  4821.7 1332.94  4864.1 1329.21
  4873.6 1327.31  4881.9 1326.66    4892 1323.83  4894.9 1323.74  4909.3 1323.21
    4945 1318.37  4955.1 1315.99  4989.1 1304.09  5009.9 1301.88  5010.1 1301.38
  5013.9 1301.88  5029.2 1302.08  5034.8 1304.17  5044.3 1309.22  5066.3 1314.92
  5088.4  1318.4  5103.4 1319.44  5132.5 1323.33  5200.4 1330.17  5261.1 1334.28
  5289.5 1337.06  5331.4 1338.83  5334.5 1339.13  5353.1 1340.89    5387 1342.54
#Mann= 8 ,-1 , 0
  4655.6     .05       0  4765.5     .12       0  4873.6     .05       0
  4894.9     .12       0  5009.9     .07       0  5013.9     .12       0
  5331.4     .05       0  5334.5     .12       0
Bank Sta=5009.9,5013.9
XS Rating Curve= 0 ,0
Exp/Cntr=0.3,0.1

Type RM Length L Ch R = 1 ,21720   ,253,253,253
BEGIN DESCRIPTION:
Mapping XS f3549166
END DESCRIPTION:
XS GIS Cut Line= 3
       2867708.1     10289874.77      2868072.65     10289551.88
       2868259.2     10289206.42
#Sta/Elev= 30
  4470.1 1343.02  4540.4 1342.19  4547.1 1343.13  4618.2 1343.15  4681.8 1339.53
  4781.3 1331.21    4824 1326.65  4838.2 1323.97  4880.8 1321.17  4901.7 1318.46
  4930.2 1312.39  4936.9 1308.67  4967.1 1304.98    4979 1298.97  4989.6 1296.94
  4993.3 1294.92  4993.5 1294.42  4997.3 1294.92  5023.9 1296.95  5046.6 1304.38
  5055.2 1310.06  5060.9 1309.19  5069.3 1315.45  5077.1 1319.27  5082.8 1318.34
    5099 1319.47  5104.7  1317.2  5139.6 1321.84  5246.5 1334.08  5349.7 1341.19
#Mann= 4 ,-1 , 0
  4470.1     .12       0  4993.3     .07       0  4997.3     .12       0
  5139.6     .05       0
Bank Sta=4993.3,4997.3
XS Rating Curve= 0 ,0
Exp/Cntr=0.3,0.1

Type RM Length L Ch R = 1 ,21467   ,467,467,467
BEGIN DESCRIPTION:
Mapping XS 38777c95
END DESCRIPTION:
XS GIS Cut Line= 4
      2867935.81     10289826.09      2868212.76     10289753.56
      2868357.84     10289562.31      2868597.89     10289207.17
#Sta/Elev= 30
  4585.6 1334.14  4709.5 1326.78  4811.1 1316.51  4888.1 1303.54  4917.2 1301.83
  4952.6 1292.75  4981.7  1289.4  5000.5 1283.08  5000.8 1282.58  5004.5 1283.08
  5017.1 1284.27  5023.4 1291.53  5037.9 1301.73  5052.5 1309.22  5060.7 1310.63
    5117 1315.84    5132 1314.23    5138 1311.21  5146.9  1312.9    5153 1310.53
  5167.9  1312.2    5174 1309.55  5182.9 1312.26  5188.9 1310.43  5203.9 1316.49
  5209.9 1315.46  5254.8 1324.74    5306 1331.21  5347.8 1335.86  5540.6 1344.16
#Mann= 4 ,-1 , 0
  4585.6     .12       0  5000.5     .07       0  5004.5     .12       0
    5306     .05       0
Bank Sta=5000.5,5004.5
XS Rating Curve= 0 ,0
Exp/Cntr=0.3,0.1

Type RM Length L Ch R = 1 ,21000   ,500,500,500
BEGIN DESCRIPTION:
CALVERT CREEK 42.0
END DESCRIPTION:
XS GIS Cut Line= 3
      2868255.67     10290053.11      2868470.44     10290081.26
      2868705.66     10290053.11
#Sta/Elev= 30
  4783.4 1308.24  4813.7 1307.22  4833.8 1304.78  4894.1 1300.72  4904.4 1298.68
  4934.7 1296.62  4944.8 1295.31  4954.9 1292.28  4964.9 1286.56  4972.9 1280.75
  4977.9 1281.44  4995.1 1275.62    5000 1275.62  5003.3 1274.32  5003.5 1273.82
    5007 1273.82  5007.3 1274.32  5028.5 1278.18  5035.5 1278.67  5055.6 1278.49
  5075.8 1280.47  5095.9 1280.48  5105.8 1283.62  5110.8 1284.44  5116.1  1286.9
  5136.2 1290.33  5166.4 1297.89  5186.6 1300.84  5206.7 1305.23  5236.9 1308.58
#Mann= 3 ,-1 , 0
  4783.4     .12       0  5003.3     .07       0  5007.3     .12       0
Bank Sta=5003.3,5007.3
XS Rating Curve= 0 ,0
Exp/Cntr=0.3,0.1

Type RM Length L Ch R = 1 ,20500   ,500,500,500
BEGIN DESCRIPTION:
CALVERT CREEK 41.0
END DESCRIPTION:
XS GIS Cut Line= 3
      2868509.49     10290637.27      2868748.85     10290469.68
      2868934.89     10290152.52
#Sta/Elev= 30
  4707.8 1316.49  4734.4 1313.16  4758.4  1310.4  4844.7 1294.78  4865.6 1289.21
  4880.4 1288.39  4895.2 1285.52  4910.1 1282.01  4937.1 1271.66  4945.8 1271.18
  4951.9 1268.25  4966.7 1266.75  4972.8 1263.34    5000  1263.6  5016.2 1261.98
  5016.5 1261.48  5020.5 1261.98  5045.7 1265.87  5067.1 1266.11  5082.8 1268.22
  5098.5 1272.23  5104.3 1272.35  5135.1 1278.83  5147.3 1282.32  5205.9 1293.26
  5215.8 1295.42  5221.6 1298.03  5237.2 1296.91  5333.5 1305.68  5367.7 1308.26
#Mann= 5 ,-1 , 0
  4707.8     .05       0  4734.4     .12       0  5016.2     .07       0
  5020.5     .12       0  5333.5     .05       0
Bank Sta=5016.2,5020.5
XS Rating Curve= 0 ,0
Exp/Cntr=0.3,0.1

Type RM Length L Ch R = 1 ,20000   ,372,372,372
BEGIN DESCRIPTION:
CALVERT CREEK 40.0
END DESCRIPTION:
XS GIS Cut Line= 3
      2868805.69     10290853.11       2869137.2     10290740.23
      2869255.72      10290703.1
#Sta/Elev= 30
  4649.8  1293.5  4696.8 1289.79  4754.3 1279.37  4759.5  1279.5  4785.6  1274.7
  4790.9 1275.25  4808.3 1271.97    4817 1268.94  4822.3 1269.48  4848.3 1266.01
  4853.6  1266.7  4871.6 1265.03  4892.8 1259.49  4911.1 1256.67  4942.4  1256.3
  4956.1 1255.13  4973.8 1251.44  4979.1 1251.84  4994.4 1249.55  4994.7 1249.05
  4998.8 1249.55  5019.4 1252.35  5029.9 1257.63  5037.8 1264.83  5050.8 1269.63
  5070.3 1272.51  5075.5    1275  5102.7 1276.88  5113.7 1279.82  5124.2 1279.58
#Mann= 3 ,-1 , 0
  4649.8     .12       0  4994.4     .07       0  4998.8     .12       0
Bank Sta=4994.4,4998.8
XS Rating Curve= 0 ,0
Exp/Cntr=0.3,0.1

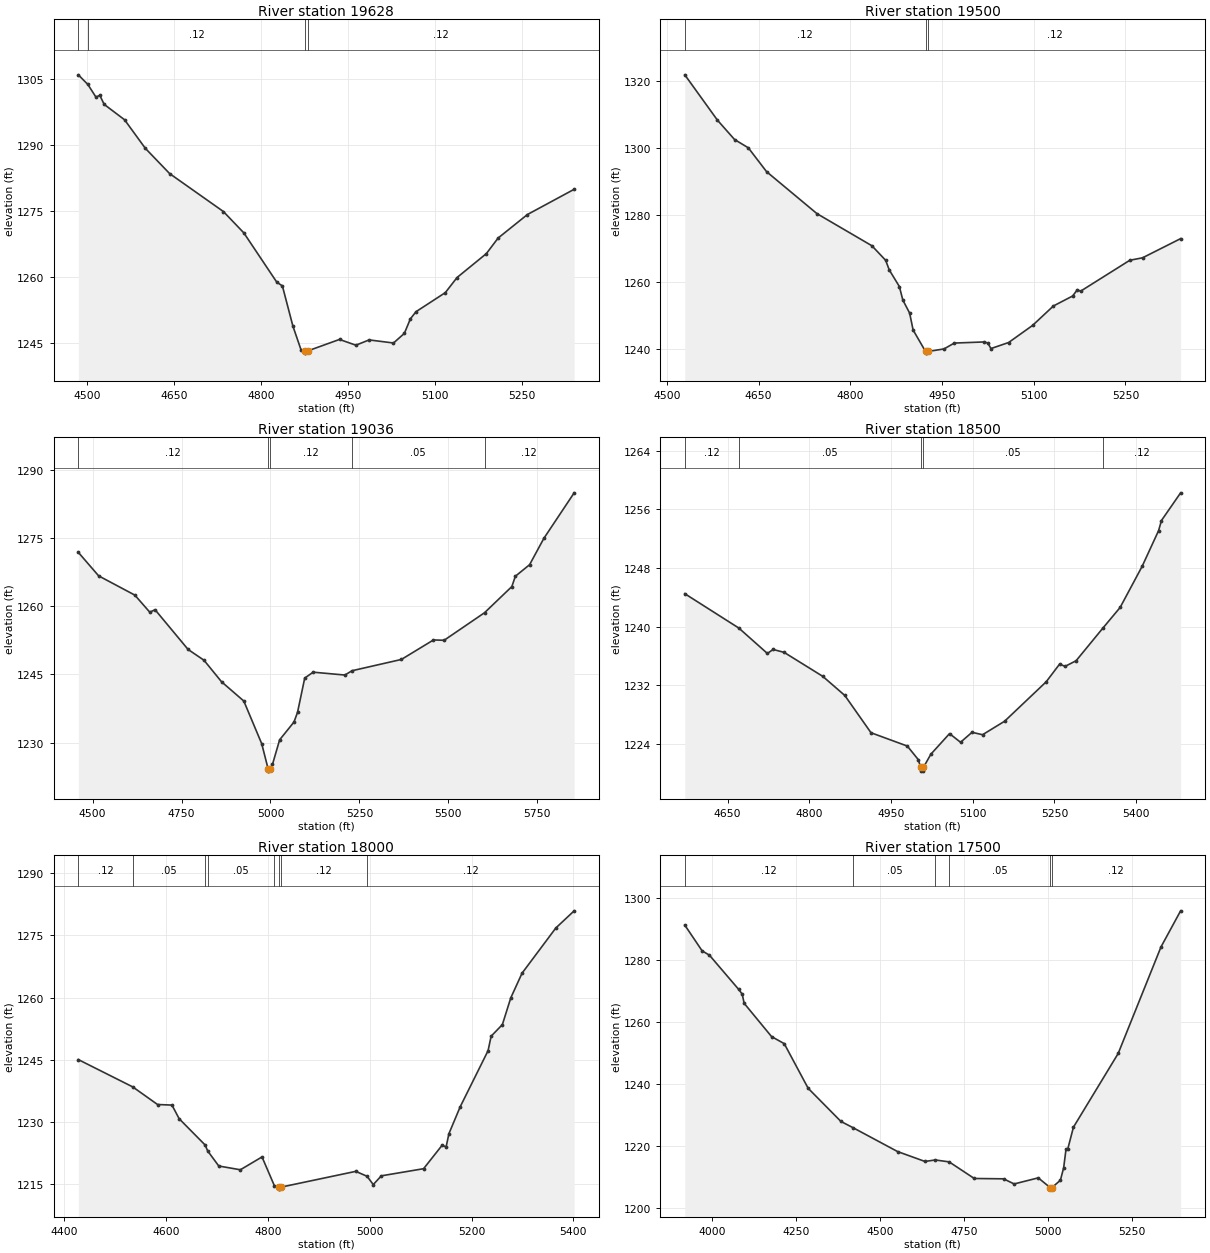
Type RM Length L Ch R = 1 ,19628   ,128,128,128
BEGIN DESCRIPTION:
Mapping XS ac190694
END DESCRIPTION:
XS GIS Cut Line= 4
       2868968.5     10291468.53       2869204.6     10291208.13
      2869319.18     10291037.99      2869360.77     10290743.43
#Sta/Elev= 30
  4485.4 1305.97  4501.8 1303.78  4515.7 1300.92  4522.4 1301.31  4529.9 1299.26
    4565 1295.77  4600.7  1289.3  4642.7 1283.54  4735.3 1274.93  4770.5 1270.08
  4827.2  1258.9  4836.9 1258.04    4855 1248.92  4869.4 1243.38  4876.1 1243.28
  4876.4 1242.78  4880.5 1243.28  4935.3 1245.89  4963.5 1244.58  4986.3 1245.78
  5028.3 1245.08    5047 1247.26  5057.4 1250.57  5067.1 1252.19  5117.6 1256.52
  5137.8 1259.95  5188.3 1265.38  5208.5 1268.91    5259 1274.25  5339.5 1279.98
#Mann= 4 ,-1 , 0
  4485.4     .05       0  4501.8     .12       0  4876.1     .07       0
  4880.5     .12       0
Bank Sta=4876.1,4880.5
XS Rating Curve= 0 ,0
Exp/Cntr=0.3,0.1

Type RM Length L Ch R = 1 ,19500   ,464,464,464
BEGIN DESCRIPTION:
CALVERT CREEK 39.0
END DESCRIPTION:
XS GIS Cut Line= 3
      2869155.68     10291603.11      2869363.62     10291180.72
      2869455.68     10290853.11
#Sta/Elev= 30
  4529.2 1321.86  4582.6 1308.34  4610.6 1302.57  4633.1  1300.1    4663 1292.98
  4745.4 1280.47  4835.3 1270.89  4857.8 1266.55  4863.6 1263.71  4880.2 1258.74
  4885.9 1254.69    4897 1250.82  4902.7 1245.77    4923 1239.38  4923.3 1238.88
  4927.4 1239.38  4953.2 1240.13  4970.1 1241.88  5018.3 1242.21  5024.8 1241.92
    5030 1240.24  5058.9 1242.04  5098.1 1247.14  5132.2 1252.94  5163.7 1255.92
  5171.4  1257.8  5176.6 1257.34  5257.2 1266.57    5278  1267.3  5340.3 1273.02
#Mann= 3 ,-1 , 0
  4529.2     .12       0    4923     .07       0  4927.4     .12       0
Bank Sta=4923,4927.4
XS Rating Curve= 0 ,0
Exp/Cntr=0.3,0.1

Type RM Length L Ch R = 1 ,19036   ,536,536,536
BEGIN DESCRIPTION:
Mapping XS ce00f9a5
END DESCRIPTION:
XS GIS Cut Line= 4
      2869548.72     10291775.65      2869783.07     10291431.93
      2869840.36     10290931.93      2869819.53     10290458.07
#Sta/Elev= 30
  4459.9 1271.87    4517  1266.7  4618.7 1262.47  4660.7 1258.71  4675.6 1259.25
  4768.4 1250.51  4813.2 1248.13  4862.4  1243.4    4925 1239.16  4975.4 1229.76
  4993.3 1224.24  4993.6 1223.74  4997.8 1224.24  5005.6 1225.22  5025.7 1230.63
    5066 1234.54    5076 1236.67  5096.2 1244.21  5119.9 1245.51  5209.1 1244.88
  5229.2 1245.83  5367.9 1248.31  5458.1  1252.6  5488.1 1252.53  5601.6 1258.59
  5678.3 1264.34  5688.3 1266.62  5728.3 1269.16  5768.4 1274.96  5853.5 1284.97
#Mann= 5 ,-1 , 0
  4459.9     .12       0  4993.3     .07       0  4997.8     .12       0
  5229.2     .05       0  5601.6     .12       0
Bank Sta=4993.3,4997.8
XS Rating Curve= 0 ,0
Exp/Cntr=0.3,0.1

Type RM Length L Ch R = 1 ,18500   ,500,500,500
BEGIN DESCRIPTION:
CALVERT CREEK 37.0
END DESCRIPTION:
XS GIS Cut Line= 3
      2870255.68     10291753.15      2870324.14     10291330.06
      2870255.69     10290853.14
#Sta/Elev= 30
  4571.4  1244.5  4670.6 1239.81  4723.1 1236.34  4733.5 1236.89  4753.8 1236.49
  4824.7 1233.22  4865.2 1230.61  4913.3 1225.52    4980  1223.7    5000 1221.86
  5004.6 1220.78  5004.9 1220.28  5009.1 1220.28  5009.5 1220.78  5023.2 1222.59
  5057.5  1225.4  5077.7 1224.22  5098.8 1225.58  5118.1 1225.25  5158.6 1227.09
  5234.9 1232.47  5259.6 1234.89  5269.7 1234.58  5289.9 1235.35  5338.9 1239.79
  5370.7 1242.62  5411.1 1248.23  5441.4 1253.12  5446.6 1254.49  5481.8 1258.27
#Mann= 5 ,-1 , 0
  4571.4     .12       0  4670.6     .05       0  5004.6     .05       0
  5009.5     .05       0  5338.9     .12       0
Bank Sta=5004.6,5009.5
XS Rating Curve= 0 ,0
Exp/Cntr=0.3,0.1

Type RM Length L Ch R = 1 ,18000   ,500,500,500
BEGIN DESCRIPTION:
CALVERT CREEK 36.0
END DESCRIPTION:
XS GIS Cut Line= 3
      2871105.68     10291403.11      2870690.87      10291009.4
      2870505.71     10290653.15
#Sta/Elev= 30
  4428.1 1245.02  4534.9 1238.43  4583.6 1234.18  4611.9 1234.04  4626.1 1230.74
  4677.1  1224.4    4682 1222.98  4703.8 1219.34  4746.2 1218.43  4788.7 1221.53
  4812.9  1214.6  4821.8 1214.26  4822.2 1213.76  4826.7 1214.26  4972.8 1218.05
  4994.9 1216.86  5007.1 1214.86    5023 1216.97  5105.9 1218.69  5142.3 1224.35
  5150.1 1223.94  5155.7 1227.16  5177.8 1233.64  5232.5 1247.17  5238.5 1250.66
  5260.6 1253.47  5277.1 1259.92  5299.2 1265.87  5365.6 1276.79  5401.5 1280.92
#Mann= 8 ,-1 , 0
  4428.1     .12       0  4534.9     .05       0  4677.1     .12       0
    4682     .05       0  4812.9     .12       0  4821.8     .07       0
  4826.7     .12       0  4994.9     .12       0
Bank Sta=4821.8,4826.7
XS Rating Curve= 0 ,0
Exp/Cntr=0.3,0.1

Type RM Length L Ch R = 1 ,17500   ,293,293,293
BEGIN DESCRIPTION:
CALVERT CREEK 35.0
END DESCRIPTION:
XS GIS Cut Line= 3
      2871605.67     10291703.09      2871085.32     10290754.08
      2870905.67     10290403.09
#Sta/Elev= 30
  3917.7 1291.33  3969.3 1283.03  3991.1 1281.63  4078.4 1270.58  4088.7 1269.08
  4094.5 1266.12    4176 1255.41  4213.9 1253.12    4285 1238.75  4382.6 1228.06
  4420.1 1225.96  4551.3 1218.35  4632.9 1215.16  4663.7 1215.64    4705 1215.02
  4779.8 1209.67    4867 1209.56  4898.5 1207.91  4970.3 1209.87  5005.8 1206.74
  5006.2 1206.24  5011.1 1206.74  5036.3 1209.11    5046 1213.13  5052.9 1219.02
  5058.5 1219.29  5075.1  1226.2  5208.3 1249.95  5335.9 1284.31  5394.3 1295.93
#Mann= 6 ,-1 , 0
  3917.7     .12       0  4420.1     .05       0  4663.7     .12       0
    4705     .05       0  5005.8     .03       0  5011.1     .12       0
Bank Sta=5005.8,5011.1
XS Rating Curve= 0 ,0
Exp/Cntr=0.3,0.1

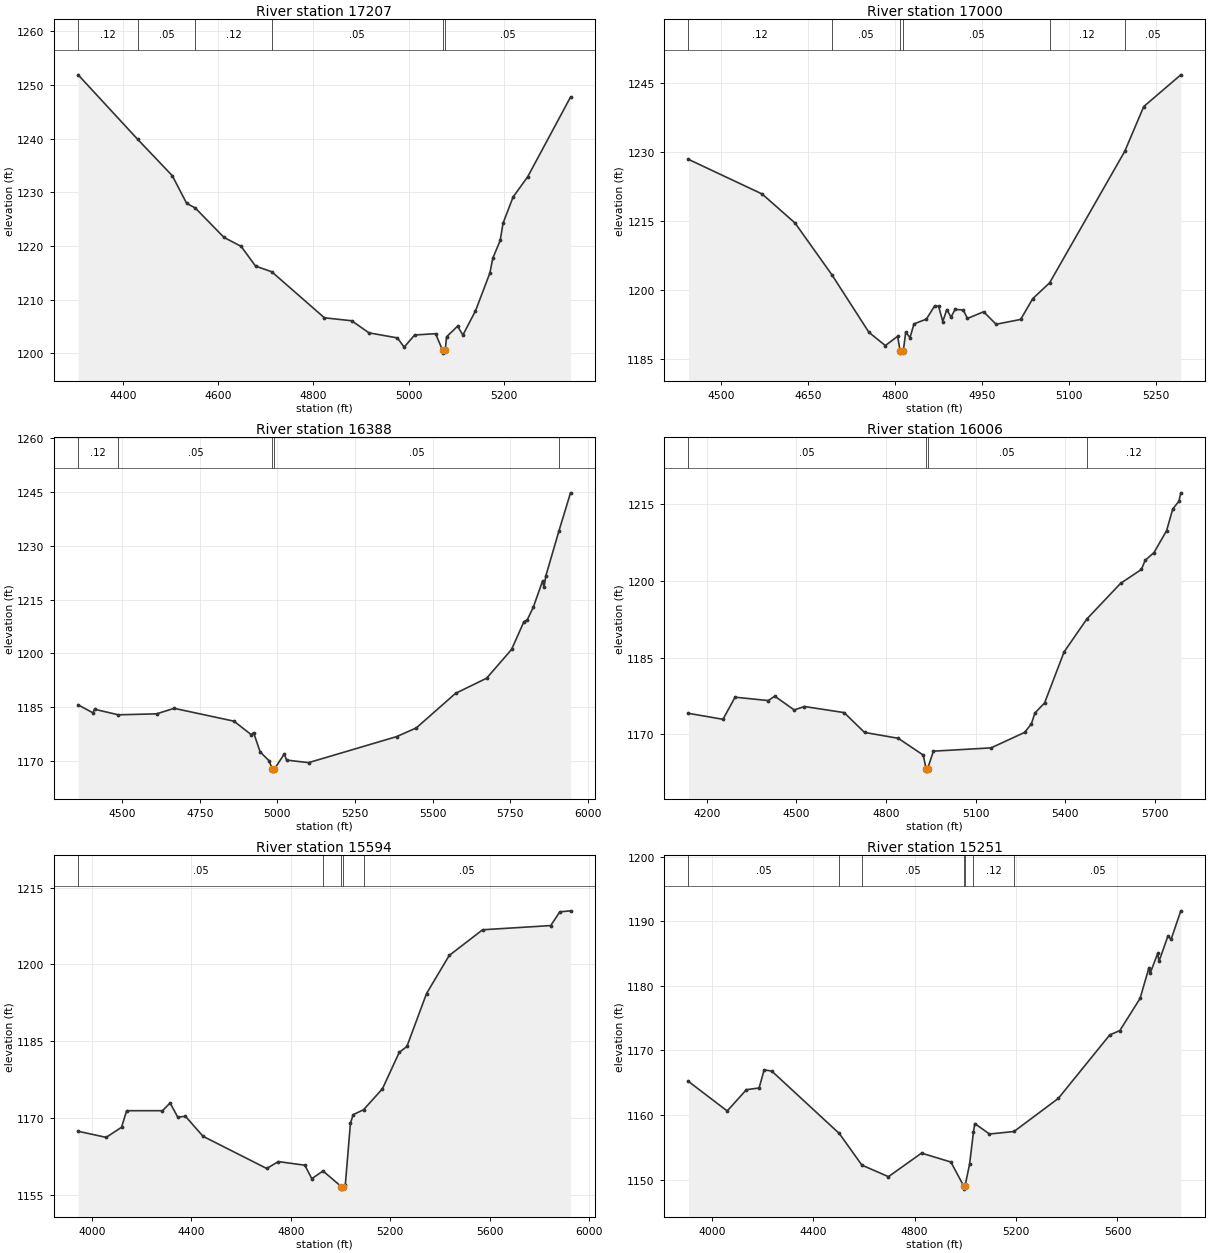
Type RM Length L Ch R = 1 ,17207   ,207,207,207
BEGIN DESCRIPTION:
Mapping XS f4c5bff5
END DESCRIPTION:
XS GIS Cut Line= 4
      2871746.27     10291367.87       2871392.1     10290829.66
      2871326.13     10290683.82      2871204.62     10290489.42
#Sta/Elev= 30
  4306.5  1251.9  4431.1 1239.92  4504.1 1233.11  4534.3 1227.95  4552.1 1227.12
  4612.6 1221.62  4648.7 1219.94  4678.9 1216.27    4713 1215.21  4823.5 1206.64
  4880.7 1206.09  4916.9 1203.84  4976.5  1202.9  4990.9 1201.18  5012.9 1203.44
  5056.8 1203.68  5071.7 1200.56  5072.1 1200.06    5077 1200.56  5079.9  1203.1
    5103 1205.08  5114.2 1203.43  5140.6 1207.93  5170.7 1214.95  5177.1 1217.78
  5192.5 1221.04  5198.4 1224.25  5219.6 1229.15  5250.2 1232.91  5340.1 1247.75
#Mann= 6 ,-1 , 0
  4306.5     .12       0  4431.1     .05       0  4552.1     .12       0
    4713     .05       0  5071.7     .03       0    5077     .05       0
Bank Sta=5071.7,5077
XS Rating Curve= 0 ,0
Exp/Cntr=0.3,0.1

Type RM Length L Ch R = 1 ,17000   ,612,612,612
BEGIN DESCRIPTION:
CALVERT CREEK 34.0
END DESCRIPTION:
XS GIS Cut Line= 3
      2871905.69     10291053.12      2871523.15     10290648.54
      2871305.67      10290453.1
#Sta/Elev= 30
  4443.2 1228.43  4570.4 1220.87  4627.1 1214.55  4690.6 1203.28  4754.5 1190.74
  4782.8 1187.86  4803.9 1189.87  4808.4 1186.71  4808.9 1186.21  4813.8 1186.71
    4818 1190.82  4825.3 1189.57  4832.2 1192.58  4853.6 1193.62  4867.8 1196.49
  4874.7 1196.41  4881.9  1193.1  4888.8  1195.7  4896.1 1194.05    4903 1195.73
  4917.1 1195.62  4924.4 1193.77  4952.4 1195.22  4973.8  1192.5  5016.2 1193.55
  5037.1 1198.09  5066.1 1201.52  5195.7 1230.17  5228.5 1239.93  5292.4 1246.84
#Mann= 6 ,-1 , 0
  4443.2     .12       0  4690.6     .05       0  4808.4     .05       0
  4813.8     .05       0  5066.1     .12       0  5195.7     .05       0
Bank Sta=4808.4,4813.8
XS Rating Curve= 0 ,0
Exp/Cntr=0.3,0.1

Type RM Length L Ch R = 1 ,16388   ,382,382,382
BEGIN DESCRIPTION:
Mapping XS d89d171d
END DESCRIPTION:
XS GIS Cut Line= 4
      2872220.57     10290921.52      2872126.82     10290447.55
      2871699.74      10289973.6      2871236.23     10289942.35
#Sta/Elev= 30
  4358.5  1185.6  4406.1 1183.39  4411.2 1184.39  4487.7 1182.83  4611.1  1183.1
  4667.5 1184.64  4860.1 1181.06  4916.1 1177.28  4923.6 1177.84  4944.5 1172.49
  4972.9 1170.05  4984.4 1167.61  4984.8 1167.11  4989.8 1167.61  5022.6 1171.92
  5029.7 1170.19  5100.7 1169.48    5384 1176.74  5447.5 1179.17  5573.9 1188.82
  5674.1 1193.05  5754.3 1201.07  5794.4 1208.87  5804.4 1209.25  5824.5  1212.9
    5854 1220.13    5859 1218.47  5864.6 1221.58  5907.3 1234.26  5944.2 1244.79
#Mann= 5 ,-1 , 0
  4358.5     .12       0  4487.7     .05       0  4984.4     .05       0
  4989.8     .05       0  5907.3     .12       0
Bank Sta=4984.4,4989.8
XS Rating Curve= 0 ,0
Exp/Cntr=0.3,0.1

Type RM Length L Ch R = 1 ,16006   ,412,412,412
BEGIN DESCRIPTION:
Mapping XS 72bf3bde
END DESCRIPTION:
XS GIS Cut Line= 6
      2872381.68     10290777.58      2872315.71     10290322.71
       2872228.9     10290010.21      2872138.63     10289968.55
      2871808.77     10289787.99      2871429.55     10289698.36
#Sta/Elev= 30
  4138.3 1174.12    4254 1172.95  4294.4 1177.27  4405.5 1176.61  4427.4 1177.46
  4492.5 1174.78  4526.8 1175.45  4659.8 1174.26    4728 1170.39  4841.1 1169.24
  4924.8 1165.96  4934.1 1163.33  4934.5 1162.83  4939.6 1163.33  4958.8 1166.73
  5151.8 1167.37  5264.4 1170.39  5287.2  1172.1  5298.8 1174.19  5331.1 1176.14
  5396.5 1186.11  5472.7 1192.54  5585.9 1199.51  5655.3 1202.21  5668.1    1204
  5697.6 1205.51  5739.9  1209.8  5760.5 1214.04  5781.1 1215.53  5787.4 1217.18
#Mann= 4 ,-1 , 0
  4138.3     .05       0  4934.1     .03       0  4939.6     .05       0
  5472.7     .12       0
Bank Sta=4934.1,4939.6
XS Rating Curve= 0 ,0
Exp/Cntr=0.3,0.1

Type RM Length L Ch R = 1 ,15594   ,343,343,343
BEGIN DESCRIPTION:
Mapping XS 8f05f56b
END DESCRIPTION:
XS GIS Cut Line= 5
      2872533.06     10290702.72       2872428.9     10290270.47
      2872460.15     10289957.97      2872355.99     10289572.55
      2871553.87     10289390.25
#Sta/Elev= 30
  3945.1 1167.41  4057.8 1166.22  4119.6 1168.19  4140.1 1171.43  4284.1 1171.43
    4315 1172.94  4345.9 1170.16  4376.7 1170.34  4447.4 1166.43  4703.7 1160.14
  4750.2 1161.49    4857 1160.78  4884.9 1158.16  4930.1 1159.65  5003.5 1156.61
  5003.9 1156.11    5009 1156.61  5019.6  1156.9  5040.3 1168.98  5051.3 1170.65
  5093.1 1171.62  5169.1 1175.71  5236.6 1182.82  5267.4 1183.97  5346.5 1194.32
  5437.8 1201.76  5572.1 1206.77  5845.9 1207.59  5882.7 1210.27  5925.6 1210.47
#Mann= 5 ,-1 , 0
  3945.1     .05       0  4930.1     .12       0  5003.5     .07       0
    5009     .12       0  5093.1     .05       0
Bank Sta=5003.5,5009
XS Rating Curve= 0 ,0
Exp/Cntr=0.3,0.1

Type RM Length L Ch R = 1 ,15251   ,241,241,241
BEGIN DESCRIPTION:
Mapping XS 8806283c
END DESCRIPTION:
XS GIS Cut Line= 6
      2872617.79     10290711.62      2872628.21     10290162.99
      2872638.63      10289874.8       2872728.9     10289666.46
      2872683.77     10289472.02      2872029.07     10289295.35
#Sta/Elev= 30
  3907.7 1165.21  4060.6 1160.63  4136.3 1163.93  4186.3 1164.19  4206.3    1167
  4236.3 1166.81  4502.7 1157.14  4591.9 1152.24  4696.6 1150.45    4827  1154.1
  4942.9 1152.72  4993.2 1149.02  4993.6 1148.52  4998.7 1149.02  5016.5 1152.36
    5032 1157.39    5037 1158.68  5095.1 1157.06  5191.8 1157.45  5366.4 1162.57
  5569.4 1172.41  5609.3 1173.09  5689.1 1178.07  5723.8 1182.79    5729 1181.97
  5758.6 1185.06  5763.8 1183.81  5798.5  1187.7  5811.8 1187.26  5849.7 1191.64
#Mann= 7 ,-1 , 0
  3907.7     .05       0  4502.7     .12       0  4591.9     .05       0
  4993.2     .05       0  4998.7     .05       0    5032     .12       0
  5191.8     .05       0
Bank Sta=4993.2,4998.7
XS Rating Curve= 0 ,0
Exp/Cntr=0.3,0.1