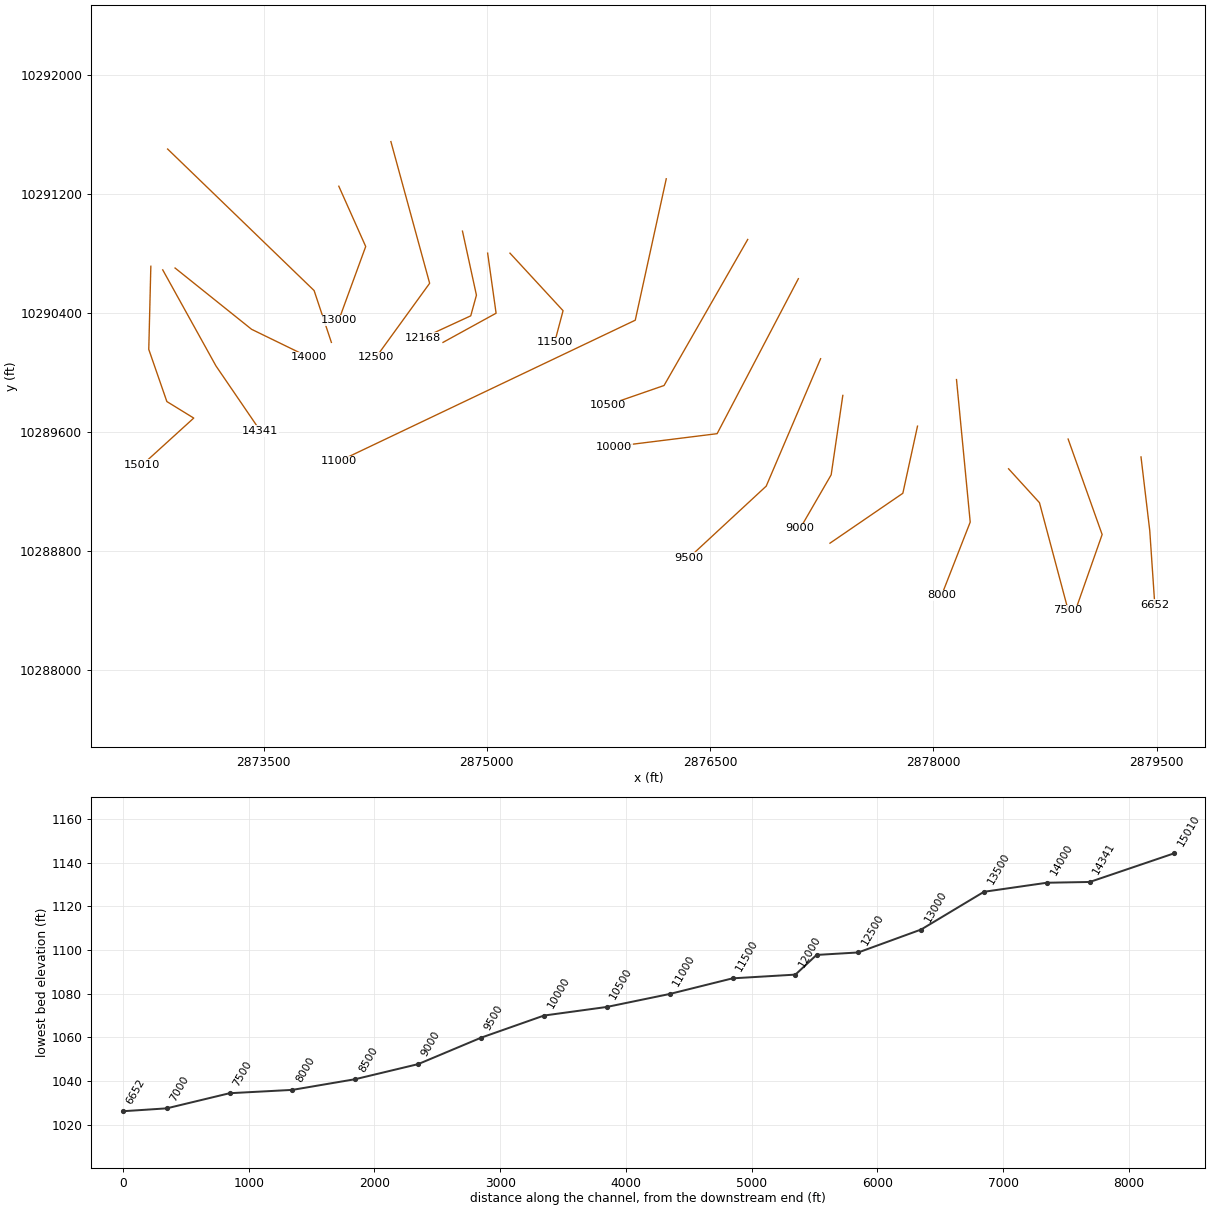
HEC-RAS study CALVERT CREEK.prj: CALVERT CREEK Base Level Engineering

--- CALVERT CREEK.g01 (geometry) --- (continued)

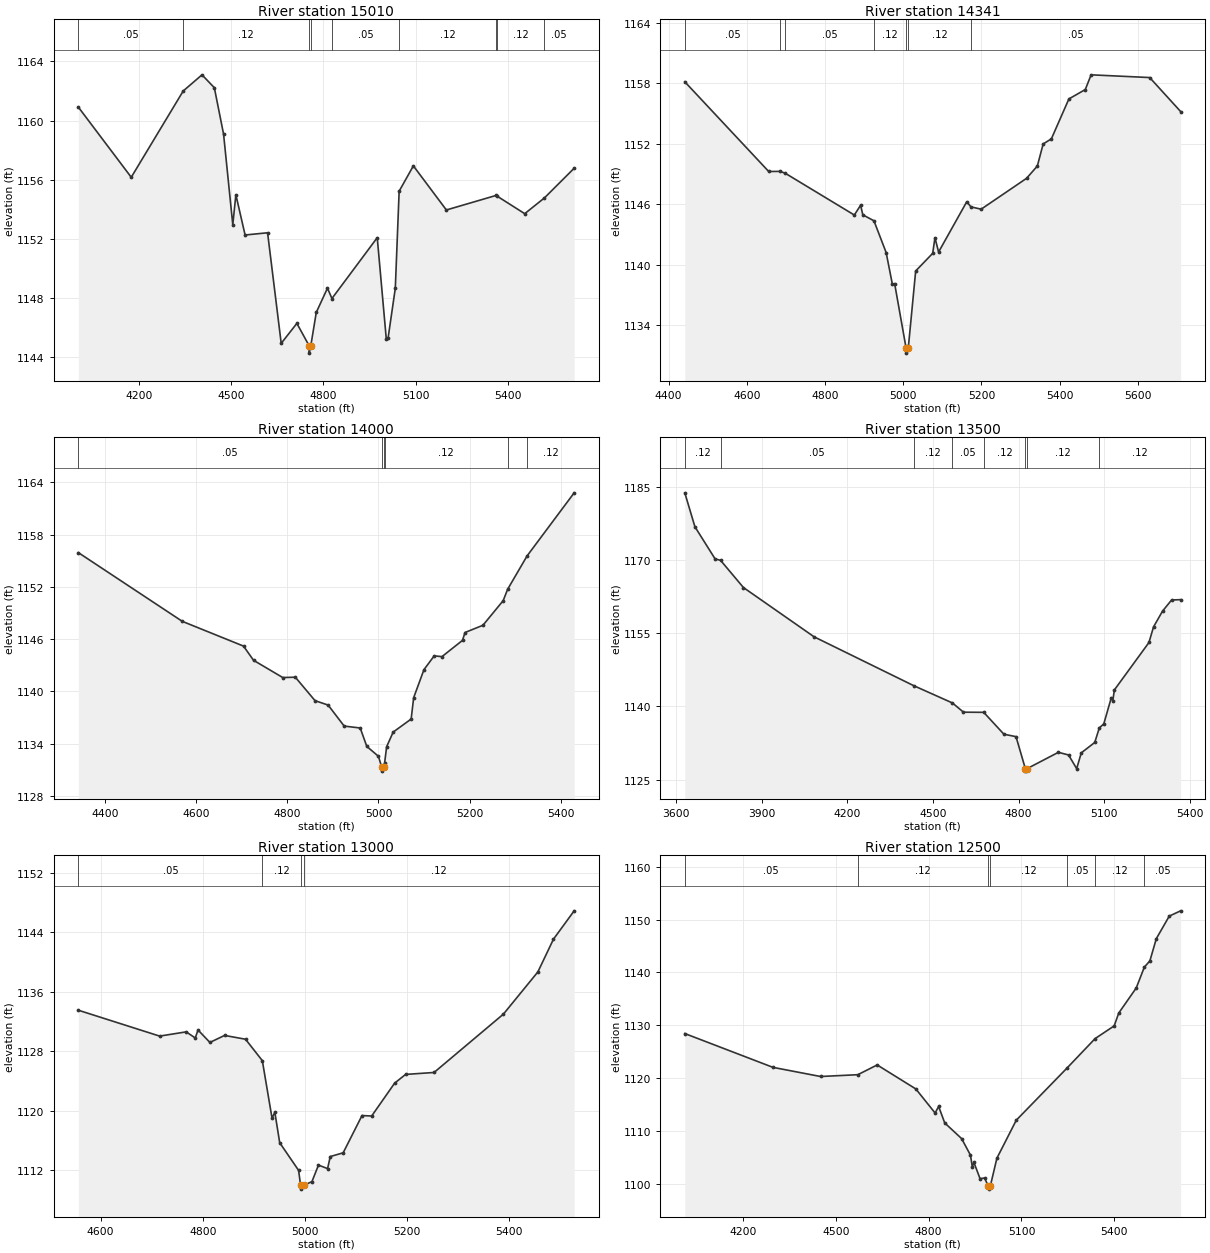
Type RM Length L Ch R = 1 ,15010   ,669,669,669
BEGIN DESCRIPTION:
Mapping XS 5267b54e
END DESCRIPTION:
XS GIS Cut Line= 5
      2872742.79     10290715.04       2872728.9     10290156.05
      2872850.43     10289805.35      2873030.99     10289694.24
      2872683.76     10289378.26
#Sta/Elev= 30
  4003.4 1160.91  4175.4 1156.17  4344.4    1162  4405.4 1163.09  4445.5 1162.22
  4475.5 1159.09  4505.5 1152.96  4515.5 1154.99  4545.5 1152.27  4618.6 1152.42
  4662.9 1144.95  4713.8  1146.3  4753.6 1144.79    4754 1144.29  4759.1 1144.79
  4776.9 1147.04  4813.3 1148.68  4827.8 1147.98  4975.1 1152.09  5004.6 1145.22
  5010.5 1145.33  5033.8 1148.67  5046.3 1155.23  5092.5 1156.94  5199.8 1153.96
  5362.6 1154.95  5364.3  1154.9  5454.5 1153.71  5518.3 1154.77  5615.2 1156.78
#Mann= 9 ,-1 , 0
  4003.4     .05       0  4344.4     .12       0  4753.6     .05       0
  4759.1     .12       0  4827.8     .05       0  5046.3     .12       0
  5362.6     .05       0  5364.3     .12       0  5518.3     .05       0
Bank Sta=4753.6,4759.1
XS Rating Curve= 0 ,0
Exp/Cntr=0.3,0.1

Type RM Length L Ch R = 1 ,14341   ,341,341,341
BEGIN DESCRIPTION:
Mapping XS 90a11493
END DESCRIPTION:
XS GIS Cut Line= 3
      2872822.68     10290690.73      2873180.29     10290044.94
      2873478.68     10289607.76
#Sta/Elev= 30
  4441.6 1158.13  4656.1 1149.23  4685.2 1149.24  4698.2 1149.06    4875 1144.91
    4891 1145.88  4896.7 1144.93  4925.1 1144.34  4956.3 1141.19  4972.3 1138.03
    4978 1138.11  5007.3 1131.71  5007.7 1131.21  5012.9 1131.71  5031.8 1139.36
  5075.3 1141.11  5081.1 1142.66  5090.4 1141.24  5162.4 1146.23    5173 1145.72
  5199.2 1145.49  5315.2 1148.55  5342.8 1149.77  5357.7 1151.96  5378.7 1152.47
  5423.5 1156.43  5465.4 1157.36  5480.3 1158.82    5630 1158.55  5709.1 1155.18
#Mann= 7 ,-1 , 0
  4441.6     .05       0  4685.2     .12       0  4698.2     .05       0
  4925.1     .12       0  5007.3     .07       0  5012.9     .12       0
    5173     .05       0
Bank Sta=5007.3,5012.9
XS Rating Curve= 0 ,0
Exp/Cntr=0.3,0.1

Type RM Length L Ch R = 1 ,14000   ,500,500,500
BEGIN DESCRIPTION:
CALVERT CREEK 28.0
END DESCRIPTION:
XS GIS Cut Line= 3
      2872905.66     10290703.13      2873419.52     10290291.18
      2873805.66     10290103.12
#Sta/Elev= 30
  4341.4 1155.94  4569.5 1148.05  4703.9 1145.21  4725.9 1143.58    4790  1141.6
  4817.6 1141.64  4860.8 1138.95  4889.6 1138.44  4924.8 1136.03    4960 1135.81
  4974.4  1133.7    5000 1132.56  5006.9 1131.36  5007.4 1130.86  5012.5 1131.36
  5013.5 1131.78    5018 1133.66  5032.3 1135.34  5071.8 1136.84  5077.3 1139.29
  5099.9 1142.51  5122.4 1144.09  5139.4    1144  5184.5 1145.87    5190 1146.77
  5229.3  1147.6  5273.8 1150.43  5283.4 1151.72  5326.2 1155.56  5429.5  1162.8
#Mann= 6 ,-1 , 0
  4341.4     .05       0  5006.9     .05       0  5012.5     .05       0
  5013.5     .12       0  5283.4     .05       0  5326.2     .12       0
Bank Sta=5006.9,5012.5
XS Rating Curve= 0 ,0
Exp/Cntr=0.3,0.1

Type RM Length L Ch R = 1 ,13500   ,500,500,500
BEGIN DESCRIPTION:
CALVERT CREEK 27.0
END DESCRIPTION:
XS GIS Cut Line= 3
      2872855.65     10291503.15       2873839.8     10290551.52
      2873955.69     10290203.08
#Sta/Elev= 30
    3631  1183.8  3666.4 1176.84  3737.2 1170.24  3756.2 1169.96  3836.2 1164.38
  4083.7 1154.27  4432.9 1144.24  4568.2  1140.7  4606.9 1138.81  4677.7 1138.78
  4748.4 1134.29  4790.8 1133.79  4823.5 1127.22    4824 1126.72  4829.2 1127.22
  4939.3 1130.58  4974.8 1130.03  5003.2 1127.23  5019.4 1130.47  5066.5  1132.6
  5082.6  1135.6  5098.1  1136.4  5124.5 1141.79  5129.8 1141.19  5135.3 1143.38
  5256.4 1153.11  5272.3  1156.3  5303.9 1159.54  5335.6 1161.82  5367.2 1161.89
#Mann= 8 ,-1 , 0
    3631     .12       0  3756.2     .05       0  4432.9     .12       0
  4568.2     .05       0  4677.7     .12       0  4823.5     .05       0
  4829.2     .12       0  5082.6     .12       0
Bank Sta=4823.5,4829.2
XS Rating Curve= 0 ,0
Exp/Cntr=0.3,0.1

Type RM Length L Ch R = 1 ,13000   ,500,500,500
BEGIN DESCRIPTION:
CALVERT CREEK 26.0
END DESCRIPTION:
XS GIS Cut Line= 3
       2874005.7     10291253.08       2874186.4     10290847.85
      2874005.69     10290353.12
#Sta/Elev= 30
  4556.3 1133.49  4715.4 1130.01  4767.4 1130.58  4785.1 1129.76  4790.6 1130.83
  4813.8 1129.16  4842.5  1130.1  4883.5 1129.59  4916.4 1126.71  4935.4 1118.98
  4940.9 1119.77  4950.4 1115.68  4987.4 1111.96  4991.3 1109.94  4991.8 1109.44
  4997.2 1109.94  5013.5 1110.45  5026.3 1112.67  5044.1  1112.2  5049.4 1113.82
  5074.6 1114.32  5111.5 1119.33  5130.4 1119.27  5175.4 1123.69  5196.8 1124.86
  5252.5 1125.12  5388.3 1132.97  5455.7 1138.64  5486.2 1143.04  5526.7 1146.85
#Mann= 4 ,-1 , 0
  4556.3     .05       0  4916.4     .12       0  4991.3     .07       0
  4997.2     .12       0
Bank Sta=4991.3,4997.2
XS Rating Curve= 0 ,0
Exp/Cntr=0.3,0.1

Type RM Length L Ch R = 1 ,12500   ,332,332,332
BEGIN DESCRIPTION:
CALVERT CREEK 25.0
END DESCRIPTION:
XS GIS Cut Line= 3
      2874355.67     10291553.15      2874615.94     10290600.46
       2874255.7     10290103.13
#Sta/Elev= 30
  4012.4 1128.42  4297.3 1122.01  4450.9 1120.28  4571.3 1120.62  4633.9 1122.47
  4758.8 1117.92    4821 1113.36  4832.4  1114.6  4852.1 1111.48  4906.7 1108.51
  4935.1 1105.39  4941.2 1103.18  4946.4 1103.99  4966.2 1100.92  4980.9 1101.05
  4993.1 1099.44  4993.6 1098.94    4999 1099.44  5020.6  1104.8  5083.2    1112
  5246.6 1121.85    5338 1127.47  5399.5 1129.87  5414.2  1132.3  5470.7 1137.05
  5496.9    1141  5514.8 1142.19  5535.6  1146.4  5577.4 1150.67  5614.1 1151.67
#Mann= 7 ,-1 , 0
  4012.4     .05       0  4571.3     .12       0  4993.1     .07       0
    4999     .12       0  5246.6     .05       0    5338     .12       0
  5496.9     .05       0
Bank Sta=4993.1,4999
XS Rating Curve= 0 ,0
Exp/Cntr=0.3,0.1

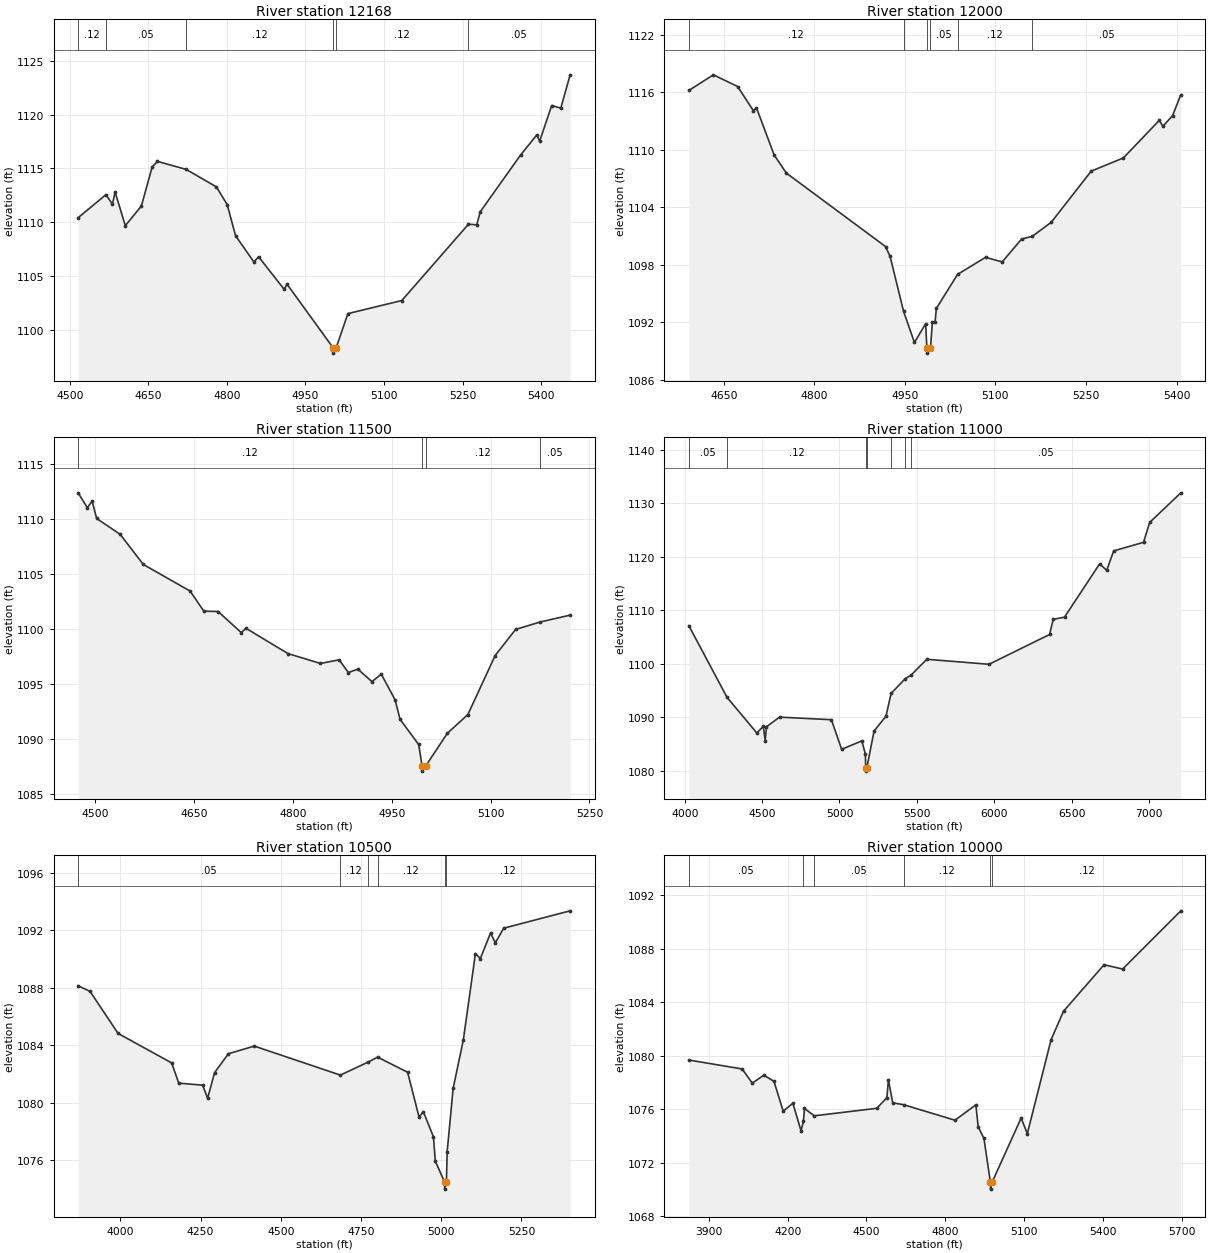
Type RM Length L Ch R = 1 ,12168   ,168,168,168
BEGIN DESCRIPTION:
Mapping XS 6a6244fa
END DESCRIPTION:
XS GIS Cut Line= 4
      2874836.55     10290951.15      2874930.29     10290520.63
       2874892.1     10290381.74      2874569.92     10290232.78
#Sta/Elev= 30
  4515.8 1110.41  4568.9 1112.56  4581.3 1111.68  4586.4  1112.8  4605.9 1109.67
  4636.6  1111.5  4657.1 1115.13  4667.3 1115.66  4722.2 1114.91  4779.9 1113.28
  4800.4 1111.64  4816.5 1108.73  4851.5 1106.29  4860.4 1106.78  4909.5 1103.73
  4914.6 1104.23  5002.7  1098.3  5003.2  1097.8  5008.6  1098.3    5031 1101.48
    5134  1102.7  5261.3 1109.81  5277.1 1109.75  5283.8 1110.97  5360.9 1116.26
  5391.7 1118.12  5397.3 1117.55  5420.2 1120.86  5437.6 1120.62  5455.4 1123.72
#Mann= 6 ,-1 , 0
  4515.8     .12       0  4568.9     .05       0  4722.2     .12       0
  5002.7     .07       0  5008.6     .12       0  5261.3     .05       0
Bank Sta=5002.7,5008.6
XS Rating Curve= 0 ,0
Exp/Cntr=0.3,0.1

Type RM Length L Ch R = 1 ,12000   ,500,500,500
BEGIN DESCRIPTION:
CALVERT CREEK 24.0
END DESCRIPTION:
XS GIS Cut Line= 3
      2875005.68     10290803.16      2875062.39     10290399.32
      2874705.69     10290203.12
#Sta/Elev= 30
  4592.2 1116.18  4632.9 1117.81    4673 1116.59  4699.2 1114.06  4704.2 1114.37
  4733.6 1109.44  4753.8 1107.56  4918.1  1099.9  4925.5 1098.89  4947.9 1093.14
  4965.9  1089.9  4984.4 1091.86  4986.5 1089.29    4987 1088.79  4992.4 1089.29
  4995.6    1092    5000    1092  5002.2 1093.45  5037.3    1097  5083.7 1098.78
  5111.2  1098.3  5143.3 1100.68  5161.1 1100.97  5192.6 1102.44  5258.7 1107.77
  5311.9 1109.14  5371.6 1113.07  5377.3 1112.44  5393.4 1113.55  5407.1 1115.73
#Mann= 6 ,-1 , 0
  4592.2     .12       0  4947.9     .05       0  4986.5     .05       0
  4992.4     .05       0  5037.3     .12       0  5161.1     .05       0
Bank Sta=4986.5,4992.4
XS Rating Curve= 0 ,0
Exp/Cntr=0.3,0.1

Type RM Length L Ch R = 1 ,11500   ,500,500,500
BEGIN DESCRIPTION:
CALVERT CREEK 23.0
END DESCRIPTION:
XS GIS Cut Line= 3
      2875155.66     10290803.13      2875512.36     10290416.29
      2875455.68     10290203.09
#Sta/Elev= 30
  4473.8 1112.36  4487.7 1111.02  4495.1 1111.59  4501.9 1110.03  4537.6 1108.59
  4572.8 1105.85  4643.7 1103.44  4664.6 1101.61  4686.2 1101.58  4721.4 1099.67
  4728.7 1100.05  4792.2 1097.76  4841.6 1096.86  4869.9 1097.19  4884.1 1096.03
  4898.3 1096.35  4919.8 1095.21    4934 1095.89    4955 1093.54  4962.4 1091.79
  4990.7  1089.5  4995.8 1087.58  4996.3 1087.08  5001.7 1087.58  5034.3 1090.52
  5065.4 1092.22  5106.8 1097.58  5137.8 1099.95  5175.4 1100.63  5220.6 1101.25
#Mann= 4 ,-1 , 0
  4473.8     .12       0  4995.8     .07       0  5001.7     .12       0
  5175.4     .05       0
Bank Sta=4995.8,5001.7
XS Rating Curve= 0 ,0
Exp/Cntr=0.3,0.1

Type RM Length L Ch R = 1 ,11000   ,500,500,500
BEGIN DESCRIPTION:
CALVERT CREEK 22.0
END DESCRIPTION:
XS GIS Cut Line= 3
      2876205.69     10291303.16      2875997.38     10290352.31
       2874005.7     10289403.12
#Sta/Elev= 30
  4026.6  1107.1  4273.7  1093.7  4466.1 1087.05  4507.8 1088.29  4520.2 1085.63
  4528.3 1088.22    4613 1090.01    4948 1089.53  5014.1    1084  5144.8 1085.57
  5167.5 1083.12    5170 1080.42  5170.5 1079.92    5176 1080.42    5224 1087.43
    5301  1090.2  5333.8 1094.44  5425.9 1097.22  5462.5 1097.85  5564.5 1100.82
    5967 1099.89  6358.4 1105.46  6381.1 1108.28  6454.7  1108.7  6681.7 1118.66
  6727.1 1117.44  6772.5 1121.08  6965.2 1122.68  7005.1  1126.4  7206.3 1131.93
#Mann= 7 ,-1 , 0
  4026.6     .05       0  4273.7     .12       0    5170     .07       0
    5176     .12       0  5333.8     .05       0  5425.9     .12       0
  5462.5     .05       0
Bank Sta=5170,5176
XS Rating Curve= 0 ,0
Exp/Cntr=0.3,0.1

Type RM Length L Ch R = 1 ,10500   ,500,500,500
BEGIN DESCRIPTION:
CALVERT CREEK 21.0
END DESCRIPTION:
XS GIS Cut Line= 3
        2876753.     10290895.31      2876190.82     10289913.24
      2875811.32     10289781.55
#Sta/Elev= 30
  3868.4 1088.14  3905.5 1087.75  3992.9 1084.82  4159.8 1082.77    4182 1081.36
  4256.2 1081.22    4272 1080.31  4293.6 1082.09  4336.8 1083.41  4417.4 1083.94
  4685.7 1081.92  4772.5 1082.83  4801.7 1083.17  4895.2 1082.12    4931 1078.99
  4944.1 1079.38  4975.7 1077.63  4981.5 1075.94  5010.2 1074.48  5010.7 1073.98
  5016.2 1074.48  5018.5 1076.59  5037.2    1081  5068.9 1084.37  5106.6 1090.38
  5121.9 1090.04  5153.6 1091.81  5168.8 1091.14  5194.7 1092.15  5401.7 1093.36
#Mann= 6 ,-1 , 0
  3868.4     .05       0  4685.7     .12       0  4772.5     .05       0
  4801.7     .12       0  5010.2     .07       0  5016.2     .12       0
Bank Sta=5010.2,5016.2
XS Rating Curve= 0 ,0
Exp/Cntr=0.3,0.1

Type RM Length L Ch R = 1 ,10000   ,500,500,500
BEGIN DESCRIPTION:
CALVERT CREEK 20.0
END DESCRIPTION:
XS GIS Cut Line= 3
      2877093.27     10290631.41       2876547.4     10289589.33
      2875855.65     10289503.11
#Sta/Elev= 30
  3823.6 1079.69  4026.8 1079.02  4065.3 1077.96  4109.4 1078.56  4147.9 1078.09
  4182.9 1075.87  4219.8 1076.46  4250.7  1074.4    4260 1075.11  4263.9 1076.07
  4301.1 1075.52  4539.4 1076.08  4577.9 1076.88  4583.6 1078.22    4600 1076.49
  4641.4 1076.35  4837.1 1075.19  4916.7 1076.34  4925.3 1074.71  4947.4 1073.83
  4972.1 1070.54  4972.6 1070.04  4978.1 1070.54    5089 1075.35  5112.6 1074.19
  5203.3 1081.22  5250.5 1083.34  5404.8 1086.81  5475.4 1086.49  5697.1 1090.84
#Mann= 6 ,-1 , 0
  3823.6     .05       0    4260     .12       0  4301.1     .05       0
  4641.4     .12       0  4972.1     .07       0  4978.1     .12       0
Bank Sta=4972.1,4978.1
XS Rating Curve= 0 ,0
Exp/Cntr=0.3,0.1

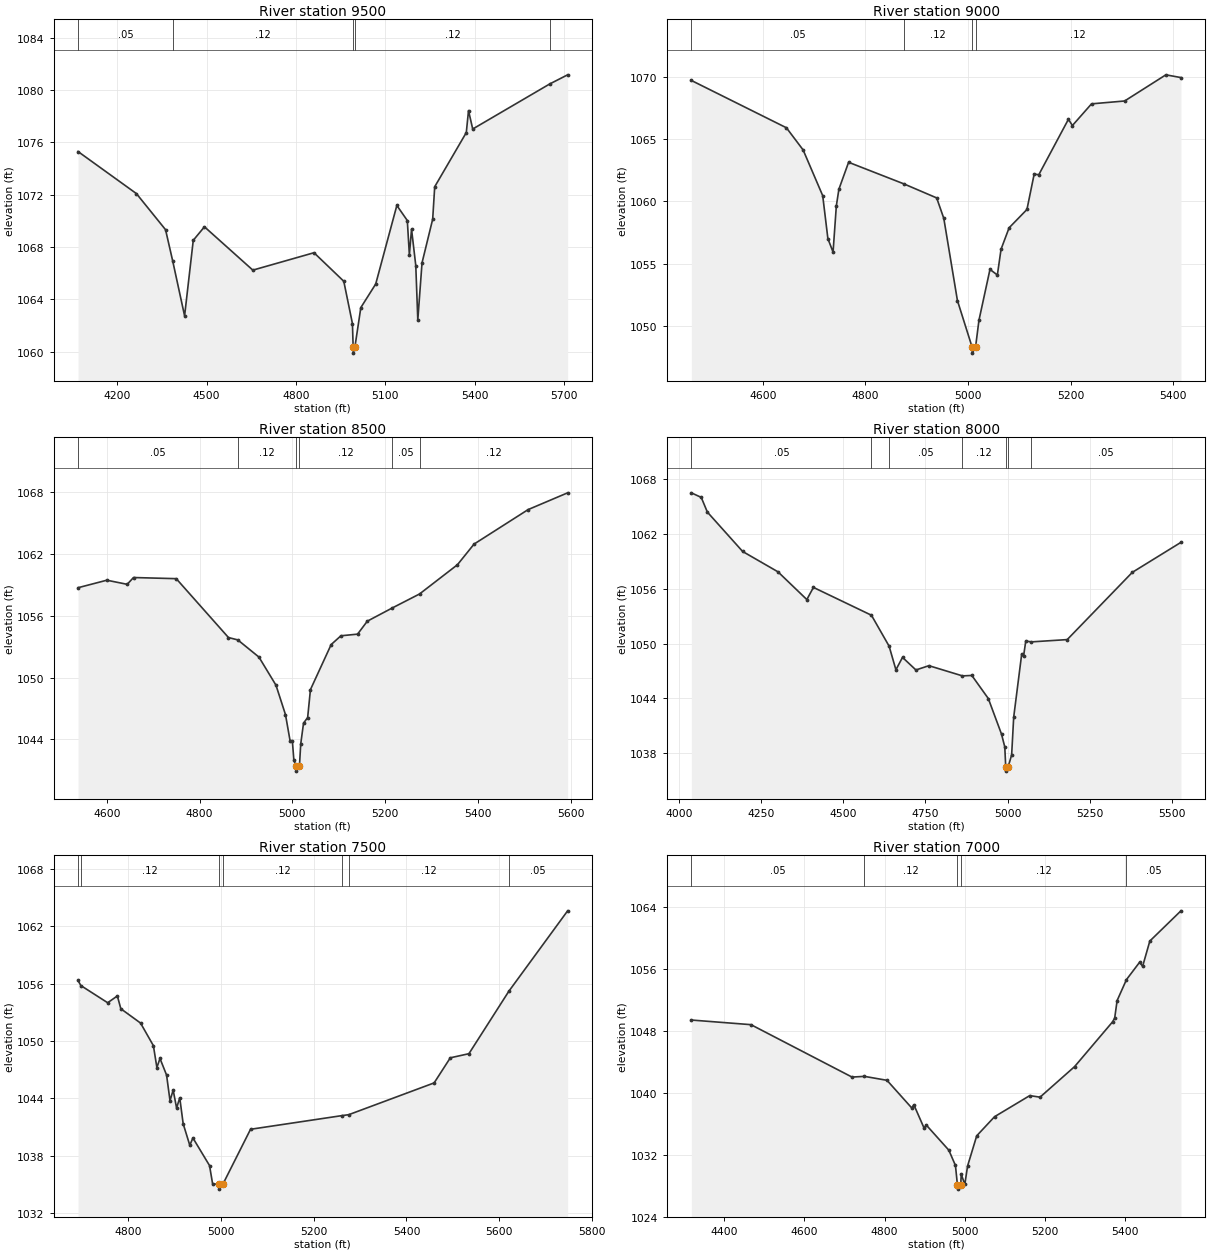
Type RM Length L Ch R = 1 ,9500    ,500,500,500
BEGIN DESCRIPTION:
CALVERT CREEK 19.0
END DESCRIPTION:
XS GIS Cut Line= 3
      2877242.55     10290093.17      2876877.22     10289236.62
      2876355.67      10288753.1
#Sta/Elev= 30
  4068.8  1075.3  4264.5 1072.09  4362.4 1069.33  4386.4 1066.94  4426.3 1062.75
  4455.4 1068.52  4492.9 1069.55  4655.2 1066.24  4860.4 1067.57  4960.3 1065.39
  4989.3 1062.16  4991.7  1060.4  4992.2  1059.9  4997.8  1060.4  5017.5 1063.38
  5067.4 1065.18  5138.3 1071.18  5173.4 1070.03  5180.3 1067.41  5187.6 1069.37
  5201.8 1066.59  5208.6 1062.44  5222.8  1066.8  5258.5 1070.13  5265.3 1072.61
  5371.3 1076.75  5378.7 1078.43  5392.8 1077.02  5651.7 1080.47  5711.2 1081.16
#Mann= 5 ,-1 , 0
  4068.8     .05       0  4386.4     .12       0  4991.7     .07       0
  4997.8     .12       0  5651.7     .05       0
Bank Sta=4991.7,4997.8
XS Rating Curve= 0 ,0
Exp/Cntr=0.3,0.1

Type RM Length L Ch R = 1 ,9000    ,500,500,500
BEGIN DESCRIPTION:
CALVERT CREEK 18.0
END DESCRIPTION:
XS GIS Cut Line= 3
      2877391.88      10289846.7      2877313.65      10289312.7
      2877105.68     10288953.11
#Sta/Elev= 30
  4460.3  1069.7  4645.8  1065.9  4678.4 1064.12  4716.6 1060.45  4726.7    1057
  4736.8 1055.92  4743.2 1059.64  4748.2 1060.97  4767.1 1063.13  4874.7  1061.4
  4938.9 1060.27  4952.8 1058.63  4979.4 1052.03  5007.9 1048.31  5008.4 1047.81
  5014.8 1048.31  5021.4 1050.45  5042.9 1054.53  5057.3 1054.08  5064.5 1056.15
  5080.2 1057.87    5115 1059.34  5129.1 1062.18  5138.1 1062.13  5195.9 1066.58
  5203.7 1066.08    5241 1067.82  5305.6 1068.05    5386 1070.15  5415.4 1069.93
#Mann= 4 ,-1 , 0
  4460.3     .05       0  4874.7     .12       0  5007.9     .07       0
  5014.8     .12       0
Bank Sta=5007.9,5014.8
XS Rating Curve= 0 ,0
Exp/Cntr=0.3,0.1

Type RM Length L Ch R = 1 ,8500    ,500,500,500
BEGIN DESCRIPTION:
CALVERT CREEK 17.0
END DESCRIPTION:
XS GIS Cut Line= 3
      2877893.68     10289639.99      2877795.15     10289188.61
       2877305.7     10288853.12
#Sta/Elev= 30
    4538 1058.73  4600.1 1059.46    4644 1059.06  4657.6 1059.72  4749.7 1059.61
  4862.3 1053.89  4882.4 1053.66    4928 1051.99  4964.7 1049.26  4985.2  1046.4
  4995.1 1043.86    5000 1043.86  5003.2 1042.01  5007.6 1041.41  5008.1 1040.91
  5015.3 1041.41  5018.1 1043.56  5024.1 1045.57    5033 1046.12    5039 1048.83
  5083.7 1053.21  5104.7 1054.06  5140.6 1054.22  5161.6 1055.48  5214.4 1056.74
  5274.1 1058.12  5355.8 1060.96  5391.7 1062.97  5508.2 1066.32  5593.4 1067.95
#Mann= 6 ,-1 , 0
    4538     .05       0  4882.4     .12       0  5007.6     .07       0
  5015.3     .12       0  5214.4     .05       0  5274.1     .12       0
Bank Sta=5007.6,5015.3
XS Rating Curve= 0 ,0
Exp/Cntr=0.3,0.1

Type RM Length L Ch R = 1 ,8000    ,500,500,500
BEGIN DESCRIPTION:
CALVERT CREEK 16.0
END DESCRIPTION:
XS GIS Cut Line= 3
      2878155.68     10289953.16      2878247.81     10288994.78
      2878055.67     10288503.08
#Sta/Elev= 30
  4037.2 1066.52  4067.4 1066.02    4086 1064.41  4193.5 1060.09    4301 1057.86
  4388.9 1054.82    4409 1056.15  4585.6  1053.1  4639.4 1049.71  4660.1 1047.12
  4680.2 1048.48    4721  1047.1  4760.6 1047.57  4862.8 1046.45  4891.2  1046.5
  4941.4 1043.97  4981.6 1040.07  4991.6 1038.66  4994.4 1036.51  4994.9 1036.01
  5002.2 1036.51  5012.5  1037.8  5018.7 1041.92  5043.2 1048.88  5048.6 1048.58
  5055.5 1050.27  5072.6 1050.18  5181.7 1050.43  5379.8  1057.8  5527.9 1061.09
#Mann= 7 ,-1 , 0
  4037.2     .05       0  4585.6     .12       0  4639.4     .05       0
  4862.8     .12       0  4994.4     .07       0  5002.2     .12       0
  5072.6     .05       0
Bank Sta=4994.4,5002.2
XS Rating Curve= 0 ,0
Exp/Cntr=0.3,0.1

Type RM Length L Ch R = 1 ,7500    ,500,500,500
BEGIN DESCRIPTION:
CALVERT CREEK 15.0
END DESCRIPTION:
XS GIS Cut Line= 3
      2878505.66     10289353.14      2878713.07     10289125.31
      2878905.67     10288403.15
#Sta/Elev= 30
  4691.9 1056.34    4698 1055.81  4755.8 1054.01  4776.7 1054.72  4784.2 1053.38
  4826.7 1051.88  4854.4 1049.51  4861.9 1047.22  4868.6 1048.17  4882.8 1046.43
  4890.2 1043.75    4897 1044.86  4904.4 1042.98  4911.2 1044.05  4918.6 1041.33
  4932.8 1039.08  4939.6 1039.84  4975.4 1036.95  4982.1 1035.02    4996 1034.98
  4996.5 1034.48    5004 1034.98  5063.8 1040.75  5261.9 1042.19  5275.5 1042.28
  5459.6 1045.61  5494.5 1048.24  5534.6 1048.67  5620.6 1055.21  5747.4 1063.64
#Mann= 7 ,-1 , 0
  4691.9     .05       0    4698     .12       0    4996     .07       0
    5004     .12       0  5261.9     .05       0  5275.5     .12       0
  5620.6     .05       0
Bank Sta=4996,5004
XS Rating Curve= 0 ,0
Exp/Cntr=0.3,0.1

Type RM Length L Ch R = 1 ,7000    ,348,348,348
BEGIN DESCRIPTION:
CALVERT CREEK 14.0
END DESCRIPTION:
XS GIS Cut Line= 3
       2878905.7     10289553.08      2879134.18     10288911.12
      2878955.67     10288403.07
#Sta/Elev= 30
  4318.6 1049.43  4467.2 1048.83  4718.9 1042.05  4749.9 1042.14  4806.1 1041.63
  4867.7 1038.06  4873.1 1038.46  4898.6 1035.44  4903.9 1035.85  4960.2 1032.59
  4976.7 1030.61  4981.7 1028.05  4982.2 1027.55  4989.8 1028.05  4991.1 1029.49
    5000 1028.15  5006.9 1030.54  5029.7 1034.45  5074.1 1036.92  5161.8 1039.65
  5187.5 1039.45  5273.5  1043.4  5368.1 1049.19  5373.4 1049.67  5379.5 1051.95
  5402.8 1054.66  5435.3 1056.89  5443.1 1056.39    5461 1059.65  5538.5 1063.56
#Mann= 5 ,-1 , 0
  4318.6     .05       0  4749.9     .12       0  4981.7     .07       0
  4989.8     .12       0  5402.8     .05       0
Bank Sta=4981.7,4989.8
XS Rating Curve= 0 ,0
Exp/Cntr=0.3,0.1

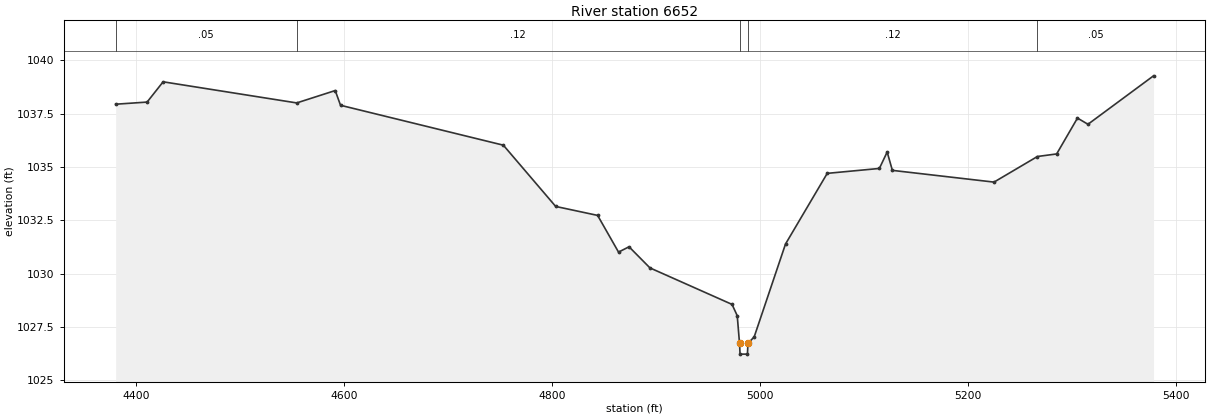
Type RM Length L Ch R = 1 ,6652    ,655,655,655
BEGIN DESCRIPTION:
Mapping XS 42467b2d
END DESCRIPTION:
XS GIS Cut Line= 3
      2879395.28     10289433.09      2879454.17     10288936.67
      2879487.83     10288440.21
#Sta/Elev= 30
  4380.6 1037.94  4410.8 1038.04  4426.2 1038.99  4554.6    1038  4591.6 1038.58
  4596.7 1037.89  4753.2 1036.02  4803.5 1033.15  4843.8 1032.73  4863.9 1031.01
    4874 1031.26  4894.1 1030.27    4973 1028.56    4978 1028.03  4980.2 1026.73
  4980.7 1026.23  4987.8 1026.23  4988.3 1026.73  4994.3 1027.04  5024.4 1031.39
  5064.5  1034.7  5114.6 1034.93  5122.1  1035.7  5127.1 1034.84  5224.8 1034.29
  5266.5 1035.49    5285 1035.61    5305 1037.29  5315.1    1037  5378.1 1039.27
#Mann= 5 ,-1 , 0
  4380.6     .05       0  4554.6     .12       0  4980.2     .07       0
  4988.3     .12       0  5266.5     .05       0
Bank Sta=4980.2,4988.3
XS Rating Curve= 0 ,0
Exp/Cntr=0.3,0.1