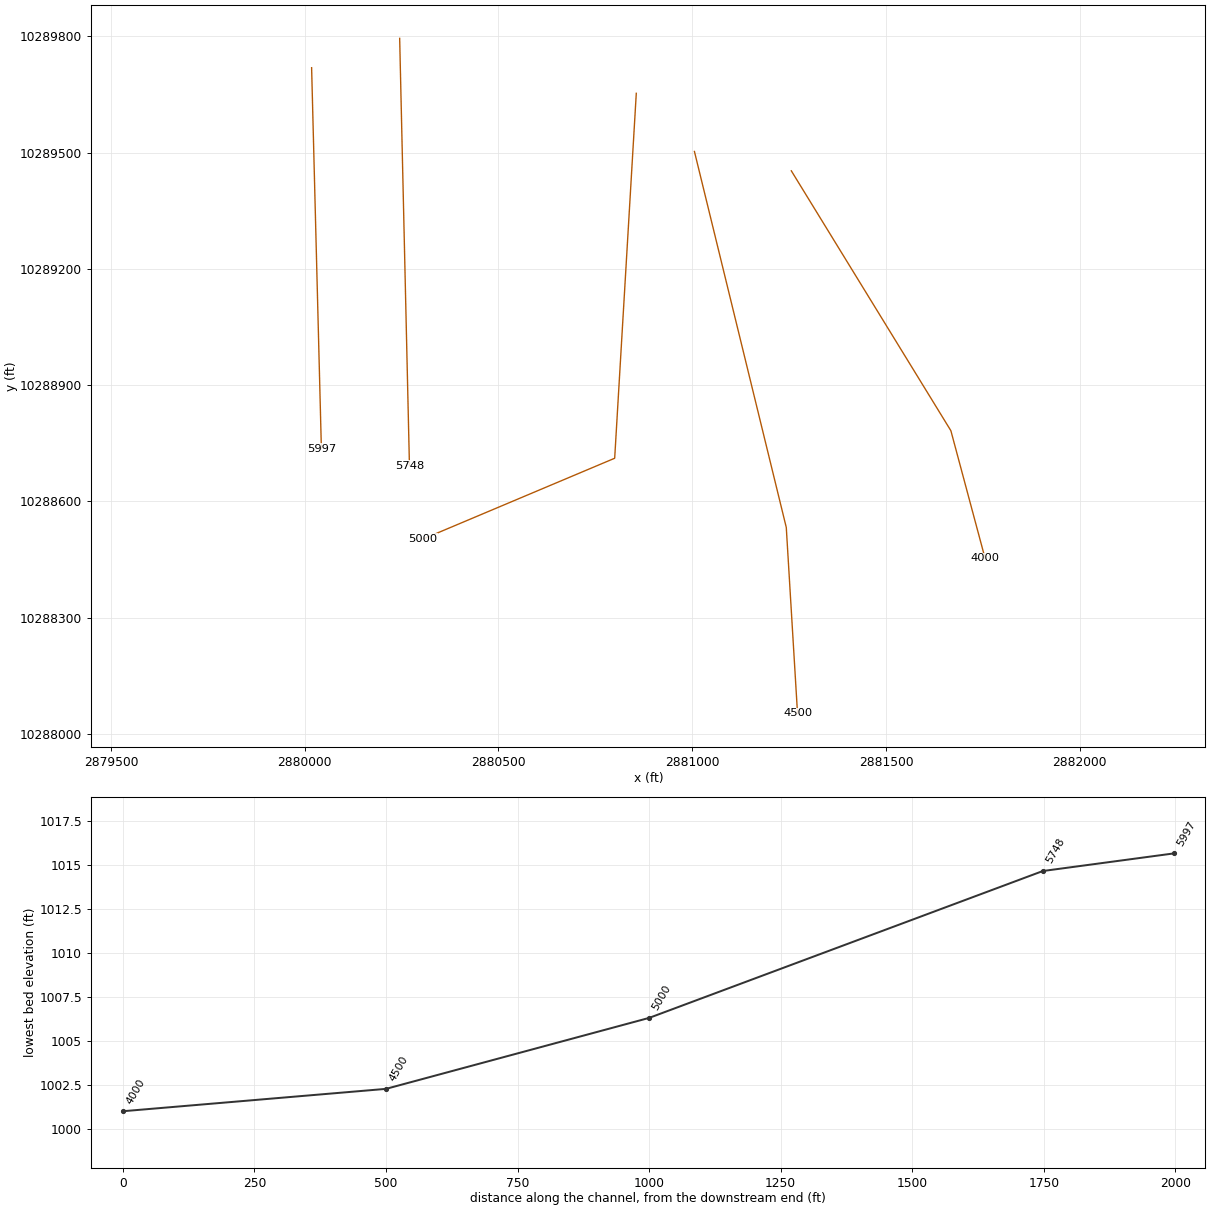
HEC-RAS study CALVERT CREEK.prj: CALVERT CREEK Base Level Engineering

--- CALVERT CREEK.g01 (geometry) --- (continued)

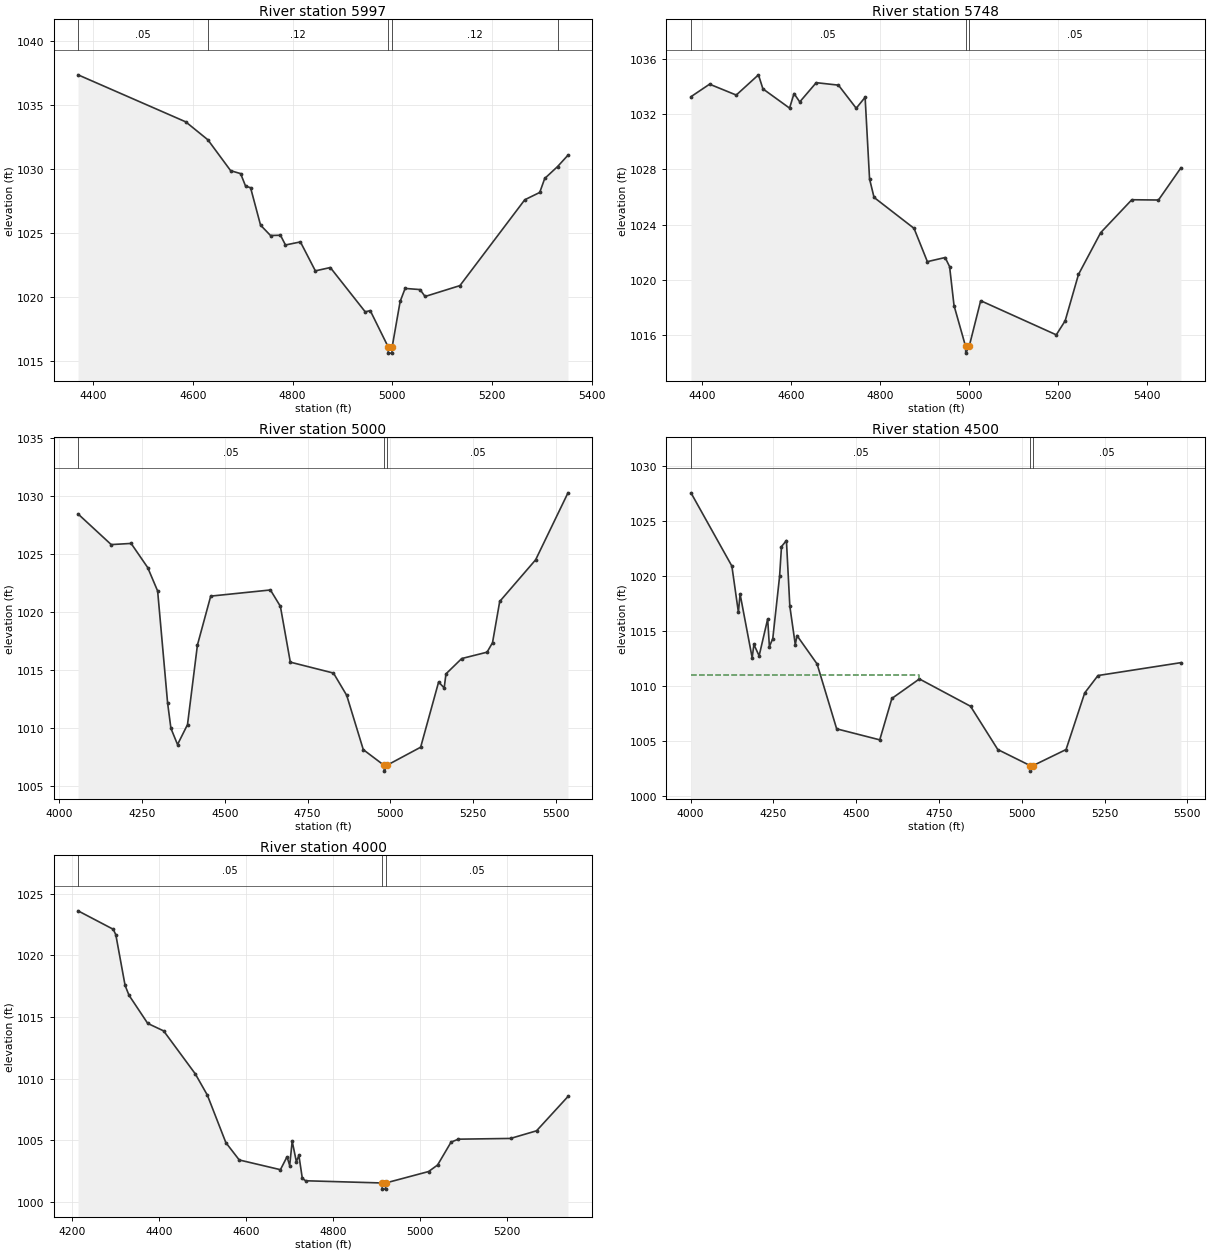
Type RM Length L Ch R = 1 ,5997    ,249,249,249
BEGIN DESCRIPTION:
Mapping XS 1c8532ea
END DESCRIPTION:
XS GIS Cut Line= 2
      2880017.94     10289719.19      2880043.14     10288736.41
#Sta/Elev= 30
  4369.4 1037.37  4585.5  1033.7  4629.9  1032.3  4675.6 1029.89  4695.6 1029.66
  4705.6 1028.68  4715.6 1028.56  4735.6 1025.64  4755.6 1024.83  4775.6 1024.85
  4785.6 1024.09  4815.6 1024.33  4845.6 1022.07  4875.6 1022.33  4945.7 1018.87
  4955.7 1018.97  4991.5 1016.15    4992 1015.65  4999.3 1015.65  4999.8 1016.15
  5015.7 1019.68  5025.7  1020.7  5055.7 1020.61  5065.7 1020.07  5135.7 1020.92
  5265.8 1027.62  5295.8 1028.19  5305.8 1029.28  5331.6 1030.21  5352.5  1031.1
#Mann= 5 ,-1 , 0
  4369.4     .05       0  4629.9     .12       0  4991.5     .07       0
  4999.8     .12       0  5331.6     .05       0
Bank Sta=4991.5,4999.8
XS Rating Curve= 0 ,0
Exp/Cntr=0.3,0.1

Type RM Length L Ch R = 1 ,5748    ,748,748,748
BEGIN DESCRIPTION:
Mapping XS c4526302
END DESCRIPTION:
XS GIS Cut Line= 2
      2880245.13     10289794.95      2880270.37     10288692.64
#Sta/Elev= 30
  4374.4 1033.29  4416.3  1034.2  4476.3 1033.41  4526.3 1034.88  4536.3 1033.86
  4596.3 1032.46  4606.3 1033.52  4619.2 1032.91  4656.3 1034.31  4706.3 1034.13
  4746.3 1032.45  4766.3 1033.25  4776.3 1027.31  4786.4 1025.97  4876.4 1023.72
  4906.4  1021.3  4946.4  1021.6  4956.4 1020.94  4966.4 1018.11  4992.3 1015.15
  4992.8 1014.65  5000.6 1015.15  5026.4 1018.46  5196.5 1015.98  5216.5    1017
  5246.5 1020.37  5296.5 1023.41  5366.5  1025.8  5426.5 1025.78    5477 1028.12
#Mann= 3 ,-1 , 0
  4374.4     .05       0  4992.3     .05       0  5000.6     .05       0
Bank Sta=4992.3,5000.6
XS Rating Curve= 0 ,0
Exp/Cntr=0.3,0.1

Type RM Length L Ch R = 1 ,5000    ,500,500,500
BEGIN DESCRIPTION:
CALVERT CREEK 10.0
END DESCRIPTION:
XS GIS Cut Line= 3
      2880855.68     10289653.12      2880799.92     10288711.47
      2880305.64     10288503.09
#Sta/Elev= 30
  4056.7 1028.47  4156.9 1025.83    4217 1025.93  4267.1 1023.85  4297.1 1021.83
  4327.2 1012.18  4337.2    1010  4357.2  1008.6  4387.3 1010.32  4417.3 1017.18
  4457.4 1021.39  4637.7 1021.92  4667.8 1020.51  4697.8  1015.7  4828.1 1014.76
  4868.1 1012.84  4918.2 1008.16    4981 1006.81  4981.5 1006.31  4989.3 1006.81
  5091.4 1008.37  5145.7 1013.99  5162.5 1013.48  5167.9 1014.69  5215.4 1016.01
    5292 1016.56  5308.5 1017.38  5330.2 1020.93  5438.7 1024.52  5536.4 1030.29
#Mann= 3 ,-1 , 0
  4056.7     .05       0    4981     .03       0  4989.3     .05       0
#XS Ineff= 2 , 0
       0    4627                       0
Permanent Ineff=
       F       F
Bank Sta=4981,4989.3
XS Rating Curve= 0 ,0
Exp/Cntr=0.3,0.1

Type RM Length L Ch R = 1 ,4500    ,500,500,500
BEGIN DESCRIPTION:
CALVERT CREEK 9.0
END DESCRIPTION:
XS GIS Cut Line= 3
      2881005.69     10289503.07      2881242.68       10288533.
      2881271.68     10288053.18
#Sta/Elev= 30
  4001.4 1027.55  4124.9  1020.9  4144.6 1016.71  4149.7 1018.36  4186.2 1012.57
  4191.4 1013.78  4207.2 1012.75    4233  1016.1  4238.2 1013.59  4248.4 1014.31
    4269 1019.97  4274.7 1022.67  4289.6 1023.22  4299.9 1017.25  4316.4 1013.76
  4321.5 1014.59  4382.2 1012.01  4441.3 1006.12  4571.4 1005.12    4608 1008.88
  4691.1 1010.65  4845.5 1008.17  4927.8 1004.24  5025.7 1002.78  5026.2 1002.28
  5034.1 1002.78  5133.9 1004.24  5190.2 1009.38  5230.3 1010.96  5480.7 1012.13
#Mann= 3 ,-1 , 0
  4001.4     .05       0  5025.7     .03       0  5034.1     .05       0
#XS Ineff= 2 , 0
       0    4691    1011               0
Permanent Ineff=
       F       F
Bank Sta=5025.7,5034.1
XS Rating Curve= 0 ,0
Exp/Cntr=0.3,0.1

Type RM Length L Ch R = 1 ,4000    ,0,0,0
BEGIN DESCRIPTION:
CALVERT CREEK 8.0
END DESCRIPTION:
XS GIS Cut Line= 3
      2881255.69      10289453.1      2881667.42     10288782.51
      2881755.68     10288453.13
#Sta/Elev= 30
  4213.1 1023.63  4294.2 1022.13  4300.1 1021.68  4321.4 1017.57  4330.4 1016.77
  4373.5 1014.48  4410.2 1013.87    4483 1010.38  4510.8 1008.65  4553.4 1004.79
  4584.2 1003.38    4679 1002.59  4694.2 1003.64  4700.3 1002.93  4706.1  1004.9
  4715.7 1003.24  4721.5 1003.75  4729.4 1001.89    4737 1001.69    4913 1001.51
  4913.5 1001.01  4920.9 1001.01  4921.4 1001.51  5020.1 1002.44  5040.8 1002.97
  5071.8 1004.83  5088.6 1005.07  5208.7 1005.13  5268.6 1005.75    5341 1008.54
#Mann= 3 ,-1 , 0
  4213.1     .05       0    4913     .03       0  4921.4     .05       0
Bank Sta=4913,4921.4
XS Rating Curve= 0 ,0
Exp/Cntr=0.3,0.1

Chan Stop Cuts=-1
Use User Specified Reach Order=0