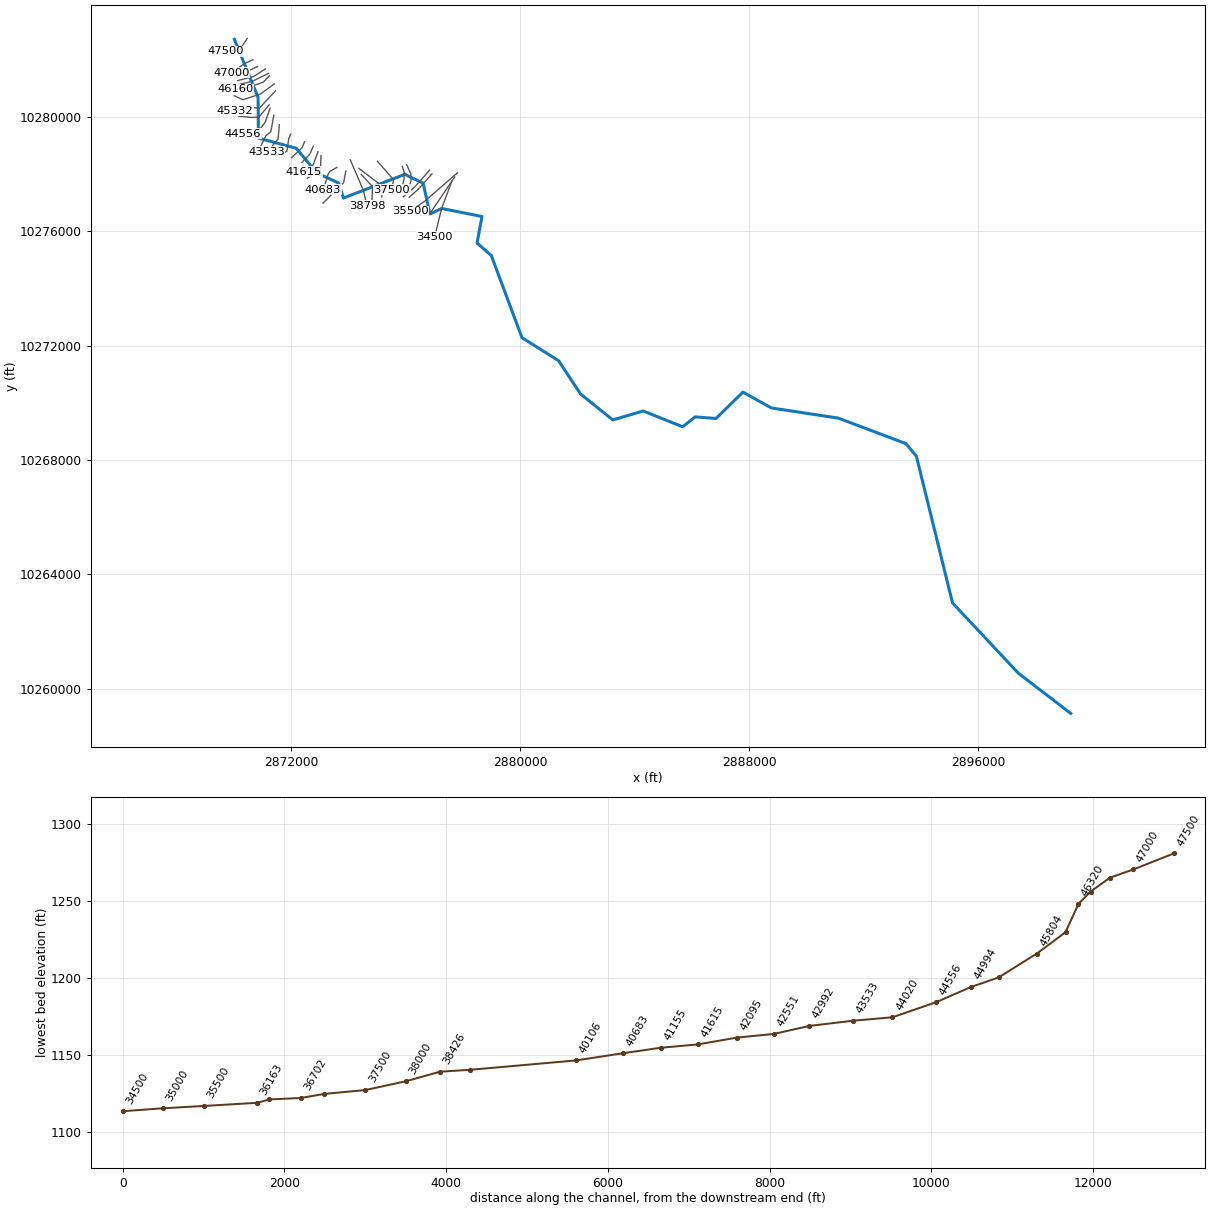
--- CAMPGROUND CREEK.prj (project) ---

Proj Title=CAMPGROUND CREEK Base Level Engineering
Current Plan=p01
Default Exp/Contr=0.3,0.1
English Units
Geom File=g01
Flow File=f01
Plan File=p01
Y Axis Title=Elevation
X Axis Title(PF)=Main Channel Distance
X Axis Title(XS)=Station
BEGIN DESCRIPTION:
CAMPGROUND CREEK
END DESCRIPTION:
DSS Export Rating Curves= 0
DSS Export Rating Curve Sorted= 0
DSS Export Volume Flow Curves= 0
DXF OffsetX= 0
DXF OffsetY= 0
DXF ScaleX= 1
DXF ScaleY= 10

--- CAMPGROUND CREEK.p01 (plan) ---

Plan Title=Multiple Run
Short Identifier=Multiple
Geom File=g01
Flow File=f01
Subcritical Flow
K Sum by GR= 0
Std Step Tol= 0.01
Critical Tol= 0.01
Num of Std Step Trials= 20
Max Error Tol= 0.3
Flow Tol Ratio= 0.001
Split Flow NTrial= 30
Split Flow Tol= 0.02
Split Flow Ratio= 0.02
Log Output Level= 0
Friction Slope Method= 1
Unsteady Friction Slope Method= 2
Unsteady Bridges Friction Slope Method= 1
Parabolic Critical Depth
Global Vel Dist=  1 , 1 , 1
Global Log Level= 0
CheckData=True
Encroach Param= -1, 0, 0, 0
BEGIN DESCRIPTION:
Multiple Run
END DESCRIPTION:

--- CAMPGROUND CREEK.f01 (steady flow) ---

Flow Title=Multiple
Number of Profiles=7
Profile Names=10-year,25-year,50-year,1pct_min,100-year,1pct_plu,500-year
River Rch & RM= CAMPGROUND CREEK,Reach-1,47500
     490     803    1109     798    1495    2800    2078
River Rch & RM= CAMPGROUND CREEK,Reach-1,36163
     746    1255    1670    1168    2264    4391    3104
River Rch & RM= CAMPGROUND CREEK,Reach-1,31513
    1077    1860    2150    1415    2900    5945    3899
River Rch & RM= CAMPGROUND CREEK,Reach-1,24500
    1374    2425    2631    1651    3559    7673    4767
River Rch & RM= CAMPGROUND CREEK,Reach-1,15500
    1750    3125    3628    2307    4966   10690    6644
Boundary for River Rch & Prof#=CAMPGROUND CREEK,Reach-1,1
Up Type=0
Dn Type=3
Dn Slope=0.005
Boundary for River Rch & Prof#=CAMPGROUND CREEK,Reach-1,2
Up Type=0
Dn Type=3
Dn Slope=0.005
Boundary for River Rch & Prof#=CAMPGROUND CREEK,Reach-1,3
Up Type=0
Dn Type=3
Dn Slope=0.005
Boundary for River Rch & Prof#=CAMPGROUND CREEK,Reach-1,4
Up Type=0
Dn Type=3
Dn Slope=0.005
Boundary for River Rch & Prof#=CAMPGROUND CREEK,Reach-1,5
Up Type=0
Dn Type=3
Dn Slope=0.005
Boundary for River Rch & Prof#=CAMPGROUND CREEK,Reach-1,6
Up Type=0
Dn Type=3
Dn Slope=0.005
Boundary for River Rch & Prof#=CAMPGROUND CREEK,Reach-1,7
Up Type=0
Dn Type=3
Dn Slope=0.005

--- CAMPGROUND CREEK.g01 (geometry) ---

Geom Title=Existing Conditions
Program Version=4.00

River Reach=CAMPGROUND CREEK,Reach-1
Reach XY= 30
        2870005.       10282716.      2870833.75       10280682.
        2870843.       10279265.      2872165.75       10278905.
      2872885.75       10278044.       2873647.5       10277692.
      2873816.75       10277166.        2875964.       10277995.
        2876603.       10277685.      2876842.25       10276609.
       2877251.5       10276800.      2878660.75       10276519.
       2878487.5       10275593.        2878986.       10275153.
      2880057.75       10272280.        2881339.       10271475.
      2882101.75       10270313.      2883232.75       10269403.
       2884298.5       10269715.       2885673.5       10269162.
      2886111.75       10269510.        2886839.       10269453.
      2887782.75       10270375.       2888776.5       10269822.
        2891121.       10269465.        2893484.       10268572.
       2893846.5       10268133.      2895109.25       10263001.
      2897411.25       10260542.      2899242.25       10259136.

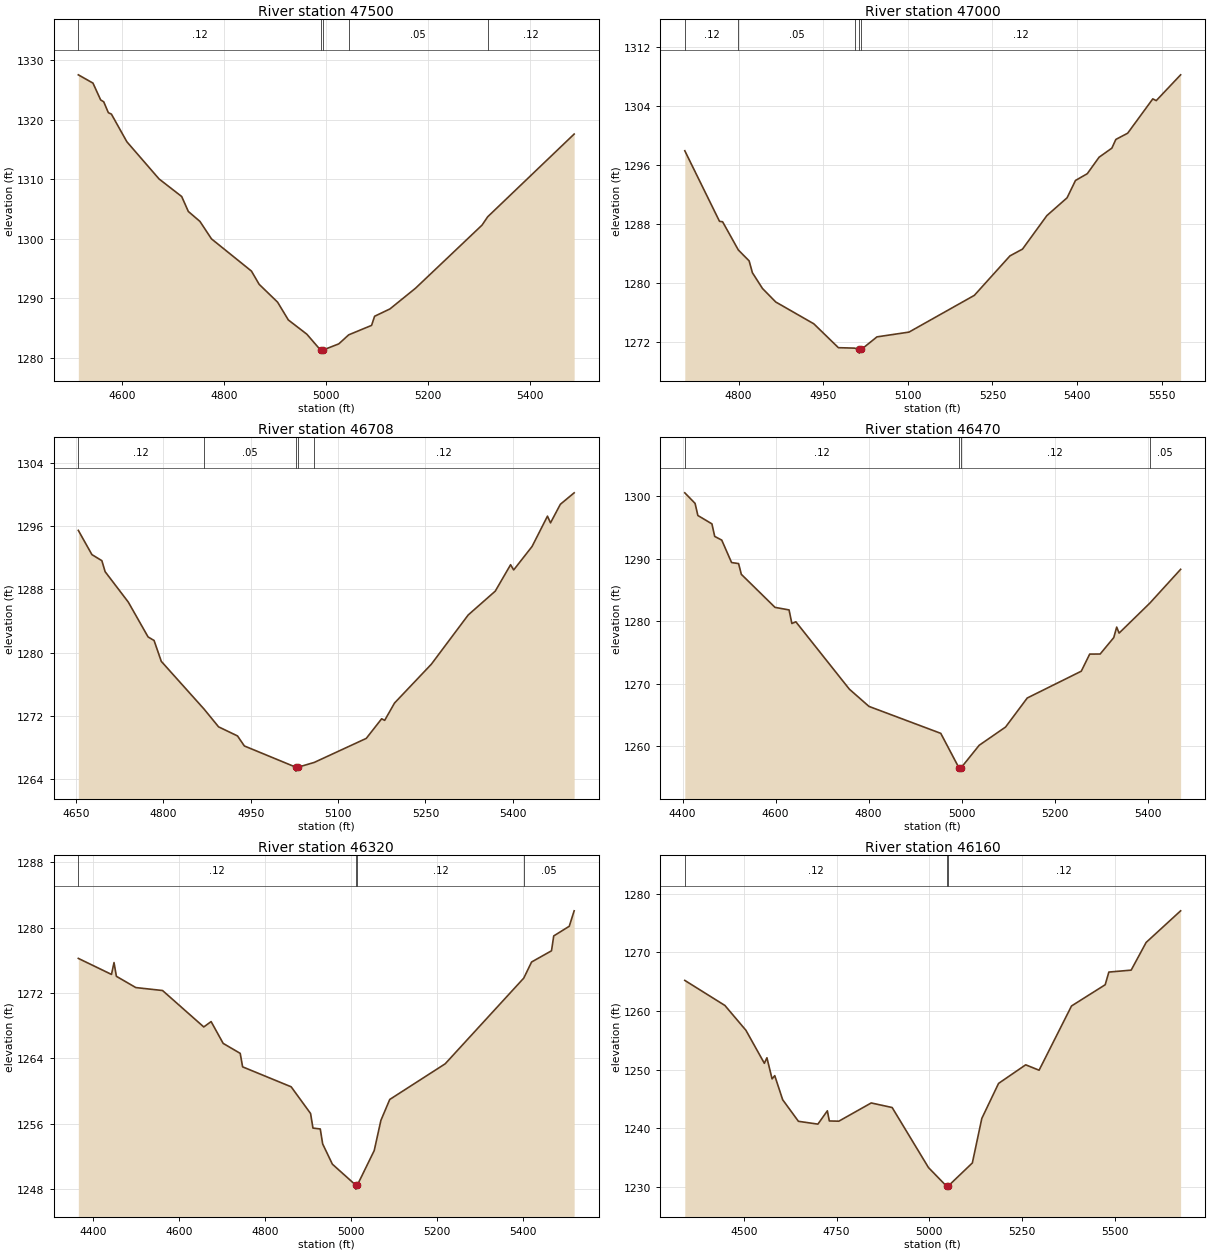
Type RM Length L Ch R = 1 ,47500   ,500,500,500
BEGIN DESCRIPTION:
CAMPGROUND CREEK 95.0
END DESCRIPTION:
XS GIS Cut Line= 3
      2870455.68     10282753.11      2870190.59     10282345.89
      2869705.68     10282303.11
#Sta/Elev= 30
  4514.1 1327.56  4542.8 1326.17  4557.9 1323.35  4563.9 1323.03    4573  1321.2
    4579 1320.96  4609.3 1316.32  4672.5 1310.07  4716.9 1307.12  4729.9 1304.61
  4752.7 1302.94  4775.3 1300.01  4853.7  1294.6  4868.8 1292.38    4905 1289.38
  4926.1 1286.39  4962.4    1284  4989.4 1281.32  4989.6 1280.82  4993.1 1280.82
  4993.4 1281.32    5025 1282.37  5044.5 1283.89  5089.4 1285.48  5095.3 1287.01
  5125.4 1288.24  5175.6 1291.72  5306.1 1302.32  5317.2 1303.72  5486.8 1317.61
#Mann= 5 ,-1 , 0
  4514.1     .12       0  4989.4     .07       0  4993.4     .12       0
  5044.5     .05       0  5317.2     .12       0
Bank Sta=4989.4,4993.4
XS Rating Curve= 0 ,0
Exp/Cntr=0.3,0.1

Type RM Length L Ch R = 1 ,47000   ,292,292,292
BEGIN DESCRIPTION:
CAMPGROUND CREEK 94.0
END DESCRIPTION:
XS GIS Cut Line= 3
      2870655.68     10282003.11      2870384.56     10281886.33
      2869905.68     10281553.11
#Sta/Elev= 30
  4704.8 1297.95  4766.3 1288.35  4771.8 1288.29  4799.7 1284.45  4818.8 1282.97
  4824.6 1281.36  4842.4 1279.22  4865.9 1277.38  4933.4 1274.41    4977 1271.16
  5005.6  1271.1  5013.6 1270.92  5013.9 1270.42  5017.6 1270.92  5045.3 1272.63
  5102.1 1273.28  5217.9 1278.28    5281 1283.65  5303.2 1284.57  5346.4 1289.13
  5382.2 1291.55  5397.1 1293.91    5418 1294.83  5438.9 1297.07  5461.6 1298.31
  5468.6 1299.49  5489.6 1300.34  5534.1 1305.01  5540.2 1304.77  5583.4 1308.28
#Mann= 5 ,-1 , 0
  4704.8     .12       0  4799.7     .05       0  5005.6     .12       0
  5013.6     .05       0  5017.6     .12       0
Bank Sta=5013.6,5017.6
XS Rating Curve= 0 ,0
Exp/Cntr=0.3,0.1

Type RM Length L Ch R = 1 ,46708   ,238,238,238
BEGIN DESCRIPTION:
Mapping XS 03b06da4
END DESCRIPTION:
XS GIS Cut Line= 3
      2870813.08     10281767.43      2870465.88     10281602.52
       2870023.2     10281454.96
#Sta/Elev= 30
  4654.2 1295.45  4677.5 1292.39  4694.6 1291.62  4700.2 1290.23  4739.9 1286.39
  4773.9 1281.98  4784.2 1281.53  4796.6 1278.89  4870.3 1272.83  4894.9 1270.61
  4927.4 1269.46  4939.2 1268.19  5027.4 1265.51  5027.6 1265.01  5031.4 1265.51
  5059.1 1266.11  5148.4 1269.15  5174.8 1271.63    5180 1271.43  5196.9 1273.62
  5260.1 1278.53  5323.4 1284.76  5369.8 1287.77  5396.1 1291.11  5401.4 1290.45
    5433 1293.42  5459.4 1297.25  5464.6  1296.4  5481.5 1298.75  5505.2  1300.2
#Mann= 5 ,-1 , 0
  4654.2     .12       0  4870.3     .05       0  5027.4     .05       0
  5031.4     .05       0  5059.1     .12       0
Bank Sta=5027.4,5031.4
XS Rating Curve= 0 ,0
Exp/Cntr=0.3,0.1

Type RM Length L Ch R = 1 ,46470   ,150,150,150
BEGIN DESCRIPTION:
Mapping XS 001f3ed8
END DESCRIPTION:
XS GIS Cut Line= 3
      2871085.37     10281682.73       2870685.9     10281421.01
      2870116.52     10281274.08
#Sta/Elev= 30
  4404.8 1300.58  4426.9 1298.89  4432.9 1296.95  4463.1 1295.61  4469.1  1293.6
  4484.2 1293.01  4505.3 1289.42  4520.4 1289.25  4526.3 1287.53  4598.7 1282.24
  4628.9 1281.83  4634.9 1279.66  4643.5 1279.93  4758.5 1269.14  4800.7 1266.38
  4954.9 1262.07  4994.2 1256.52  4994.4 1256.02  4998.2 1256.52  5037.5 1260.16
  5094.2 1263.08  5140.8 1267.73  5256.9 1272.02    5275 1274.76  5297.5 1274.77
  5326.7  1277.4    5333 1279.08  5338.2 1278.12  5404.1 1282.91  5470.4 1288.33
#Mann= 4 ,-1 , 0
  4404.8     .12       0  4994.2     .07       0  4998.2     .12       0
  5404.1     .05       0
Bank Sta=4994.2,4998.2
XS Rating Curve= 0 ,0
Exp/Cntr=0.3,0.1

Type RM Length L Ch R = 1 ,46320   ,160,160,160
BEGIN DESCRIPTION:
Mapping XS 451ef735
END DESCRIPTION:
XS GIS Cut Line= 3
      2871195.09     10281524.41      2870639.49     10281255.29
      2870119.64     10281125.33
#Sta/Elev= 30
  4366.5 1276.24  4443.6 1274.28  4449.5 1275.73    4455 1274.05  4500.2 1272.67
  4562.4 1272.31  4658.3 1267.85  4675.3 1268.51  4703.4 1265.84    4743 1264.62
  4748.6 1262.97  4861.5 1260.53  4906.7 1257.26  4912.2 1255.48  4929.2 1255.37
  4934.8 1253.54  4957.4 1251.06  5011.5 1248.51  5011.8 1248.01  5015.5 1248.51
  5054.7 1252.73  5070.2 1256.42  5090.8 1258.98  5219.7 1263.34  5402.5 1273.83
  5420.7  1275.8    5467 1277.17  5472.2 1278.99  5508.3 1280.17  5519.7 1282.06
#Mann= 4 ,-1 , 0
  4366.5     .12       0  5011.5     .07       0  5015.5     .12       0
  5402.5     .05       0
Bank Sta=5011.5,5015.5
XS Rating Curve= 0 ,0
Exp/Cntr=0.3,0.1

Type RM Length L Ch R = 1 ,46160   ,356,356,356
BEGIN DESCRIPTION:
Mapping XS d74afccc
END DESCRIPTION:
XS GIS Cut Line= 4
      2871233.71     10281447.89      2871017.54     10281222.25
      2870244.24     10280947.52      2870043.56      10280973.6
#Sta/Elev= 30
  4341.2 1265.21  4449.2 1260.94  4505.8 1256.71  4555.5 1251.08  4562.4 1252.02
  4576.3 1248.42  4583.5 1248.97  4604.9 1244.86  4647.3 1241.19  4699.7 1240.71
  4725.2 1242.98  4730.5 1241.25  4756.1 1241.21  4843.3 1244.32  4899.7 1243.54
  4997.6  1233.3  5046.3 1230.13  5046.6 1229.63  5050.3 1230.13  5115.7 1234.09
  5141.2 1241.68  5186.3 1247.65  5259.4 1250.82  5295.5  1249.9  5382.8 1260.85
  5473.5 1264.47  5483.4 1266.63  5543.5 1266.96  5583.8 1271.68  5676.7 1277.07
#Mann= 3 ,-1 , 0
  4341.2     .12       0  5046.3     .07       0  5050.3     .12       0
Bank Sta=5046.3,5050.3
XS Rating Curve= 0 ,0
Exp/Cntr=0.3,0.1

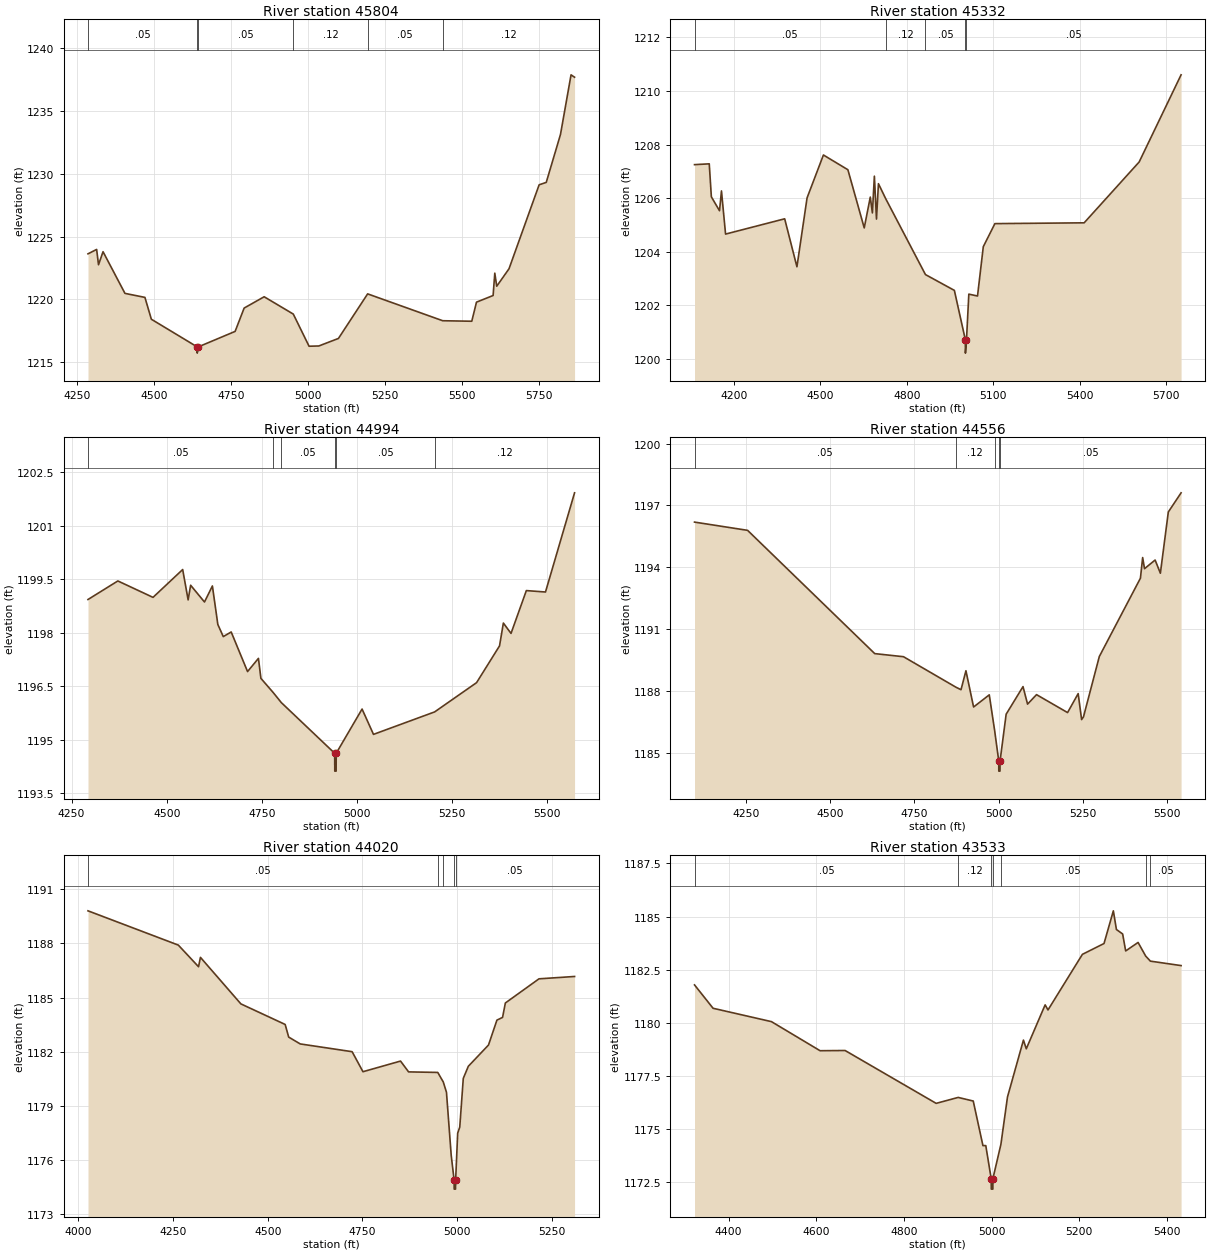
Type RM Length L Ch R = 1 ,45804   ,472,472,472
BEGIN DESCRIPTION:
Mapping XS 9a15eb46
END DESCRIPTION:
XS GIS Cut Line= 4
      2871399.99     10281157.07      2870912.65      10280804.1
      2870305.57     10280604.95      2869995.26     10280745.25
#Sta/Elev= 30
  4284.5 1223.63  4312.6 1223.98  4318.7 1222.76  4333.4  1223.8  4404.6 1220.48
  4469.5 1220.16  4490.4 1218.42  4639.2 1216.22  4639.5 1215.72  4643.2 1216.22
  4762.6 1217.45    4792 1219.31    4857 1220.21  4951.7 1218.83  5002.9 1216.27
  5034.7 1216.29  5098.4 1216.89  5193.3 1220.44  5437.3  1218.3  5531.7 1218.26
    5547 1219.78    5601 1220.31  5606.5 1222.09  5612.8 1221.05  5652.7 1222.44
  5750.6 1229.13  5773.7 1229.32    5820 1233.14  5854.3 1237.89  5865.7  1237.7
#Mann= 6 ,-1 , 0
  4284.5     .05       0  4639.2     .07       0  4643.2     .05       0
  4951.7     .12       0  5193.3     .05       0  5437.3     .12       0
Bank Sta=4639.2,4643.2
XS Rating Curve= 0 ,0
Exp/Cntr=0.3,0.1

Type RM Length L Ch R = 1 ,45332   ,338,338,338
BEGIN DESCRIPTION:
Mapping XS 4493eaf0
END DESCRIPTION:
XS GIS Cut Line= 4
      2871444.52     10280916.53      2870874.16     10280309.83
      2870580.29     10280337.38      2870033.93     10280213.42
#Sta/Elev= 30
  4063.5 1207.25  4114.6 1207.28  4121.9 1206.05  4150.2 1205.53    4157 1206.27
  4171.2 1204.66  4376.3 1205.23  4418.8 1203.44    4454 1206.01  4510.7 1207.61
  4595.6 1207.06  4652.3 1204.89  4673.3 1206.04  4680.6 1205.45  4687.5 1206.82
  4694.8 1205.22  4701.6 1206.54  4726.8 1205.98  4864.7 1203.15    4965 1202.56
  5003.1 1200.72  5003.4 1200.22  5007.1 1200.72  5015.2 1202.42  5045.3 1202.35
  5065.4 1204.19  5105.6 1205.05  5415.3 1205.08  5606.2 1207.35  5751.6  1210.6
#Mann= 5 ,-1 , 0
  4063.5     .05       0  4726.8     .12       0  4864.7     .05       0
  5003.1     .03       0  5007.1     .05       0
Bank Sta=5003.1,5007.1
XS Rating Curve= 0 ,0
Exp/Cntr=0.3,0.1

Type RM Length L Ch R = 1 ,44994   ,438,438,438
BEGIN DESCRIPTION:
Mapping XS 06e7337f
END DESCRIPTION:
XS GIS Cut Line= 4
      2871220.49     10280429.01       2870851.2     10279988.42
      2870561.93     10279988.42      2870149.73     10280034.22
#Sta/Elev= 30
  4293.1 1198.93  4371.6 1199.45    4464 1198.99    4542 1199.77  4556.3 1198.92
  4562.9 1199.33  4599.3 1198.86  4620.1 1199.31  4634.4 1198.23  4648.7 1197.89
  4669.5 1198.02  4712.5 1196.91  4741.1 1197.28  4747.6 1196.72  4780.1 1196.32
  4801.3 1196.04  4941.5 1194.62  4941.8 1194.12  4945.3 1194.12  4945.5 1194.62
  5013.5 1195.86  5043.5 1195.15  5204.3 1195.78  5314.5  1196.6  5374.8 1197.63
  5384.9 1198.27    5405 1197.98  5445.3 1199.18  5495.6 1199.14    5572 1201.92
#Mann= 6 ,-1 , 0
  4293.1     .05       0  4780.1     .12       0  4801.3     .05       0
  4941.5     .05       0  4945.5     .05       0  5204.3     .12       0
Bank Sta=4941.5,4945.5
XS Rating Curve= 0 ,0
Exp/Cntr=0.3,0.1

Type RM Length L Ch R = 1 ,44556   ,536,536,536
BEGIN DESCRIPTION:
Mapping XS a238067c
END DESCRIPTION:
XS GIS Cut Line= 5
      2871251.27     10280310.49      2871079.99     10279818.63
      2870899.86      10279578.5      2870626.21      10279561.4
      2870304.78     10279423.64
#Sta/Elev= 30
    4097 1196.19  4254.6 1195.79  4632.2 1189.81  4717.6 1189.66  4873.4 1188.18
  4888.4 1188.06    4903 1188.98  4925.7 1187.22  4972.3 1187.81  4988.4 1186.06
  5000.4 1184.61  5000.6 1184.11  5004.1 1184.11  5004.4 1184.61  5022.4 1186.87
  5072.5 1188.21    5086 1187.36  5112.6 1187.82  5204.8 1186.95  5236.3 1187.87
  5246.5 1186.61    5252 1186.74  5299.1 1189.67  5421.2 1193.47  5427.8 1194.47
  5433.3 1193.93  5464.8 1194.35  5480.4 1193.71    5504 1196.68  5541.9 1197.61
#Mann= 5 ,-1 , 0
    4097     .05       0  4873.4     .12       0  4988.4     .05       0
  5000.4     .03       0  5004.4     .05       0
Bank Sta=5000.4,5004.4
XS Rating Curve= 0 ,0
Exp/Cntr=0.3,0.1

Type RM Length L Ch R = 1 ,44020   ,487,487,487
BEGIN DESCRIPTION:
Mapping XS 7b90efab
END DESCRIPTION:
XS GIS Cut Line= 4
        2871383.     10280064.52      2871278.23     10279487.93
      2871099.15      10279336.4      2870897.13     10278918.59
#Sta/Elev= 30
  4025.5 1189.81    4264 1187.91  4317.4 1186.71  4322.4 1187.23  4429.2 1184.65
  4546.1 1183.51  4555.4 1182.81  4585.9 1182.43  4722.9    1182  4751.5 1180.89
  4850.7 1181.48    4872 1180.88    4949 1180.85  4963.6 1180.32    4972 1179.75
  4984.5 1176.26  4992.2 1174.88  4992.4 1174.38  4995.9 1174.38  4996.2 1174.88
  5001.6 1177.48  5007.1 1177.82  5016.4 1180.52  5029.7 1181.19    5083 1182.37
  5105.2 1183.75  5120.1  1183.9  5127.5  1184.7  5216.3 1186.04  5310.2 1186.17
#Mann= 5 ,-1 , 0
  4025.5     .05       0    4949     .12       0  4963.6     .05       0
  4992.2     .05       0  4996.2     .05       0
Bank Sta=4992.2,4996.2
XS Rating Curve= 0 ,0
Exp/Cntr=0.3,0.1

Type RM Length L Ch R = 1 ,43533   ,541,541,541
BEGIN DESCRIPTION:
Mapping XS 290f0867
END DESCRIPTION:
XS GIS Cut Line= 4
      2871576.23     10279735.21      2871530.77      10279230.8
      2871296.59     10278950.71      2871123.56     10278786.78
#Sta/Elev= 30
  4322.3 1181.78  4364.6 1180.68  4497.8 1180.05  4608.7 1178.68  4665.8 1178.69
  4873.5  1176.2  4923.7 1176.48  4958.1 1176.31  4980.2 1174.21  4986.7 1174.21
    4999 1172.66  4999.3 1172.16  5002.8 1172.16    5003 1172.66  5021.2 1174.27
  5036.2  1176.5  5072.6 1179.18  5079.1 1178.77  5122.1 1180.84  5128.6  1180.6
  5207.1 1183.22  5256.4 1183.73  5277.7 1185.27  5284.7 1184.39  5298.9 1184.18
  5305.8 1183.38  5334.1 1183.78  5351.4 1183.14  5362.2  1182.9  5432.2 1182.69
#Mann= 7 ,-1 , 0
  4322.3     .05       0  4923.7     .12       0    4999     .07       0
    5003     .12       0  5021.2     .05       0  5351.4     .12       0
  5362.2     .05       0
Bank Sta=4999,5003
XS Rating Curve= 0 ,0
Exp/Cntr=0.3,0.1

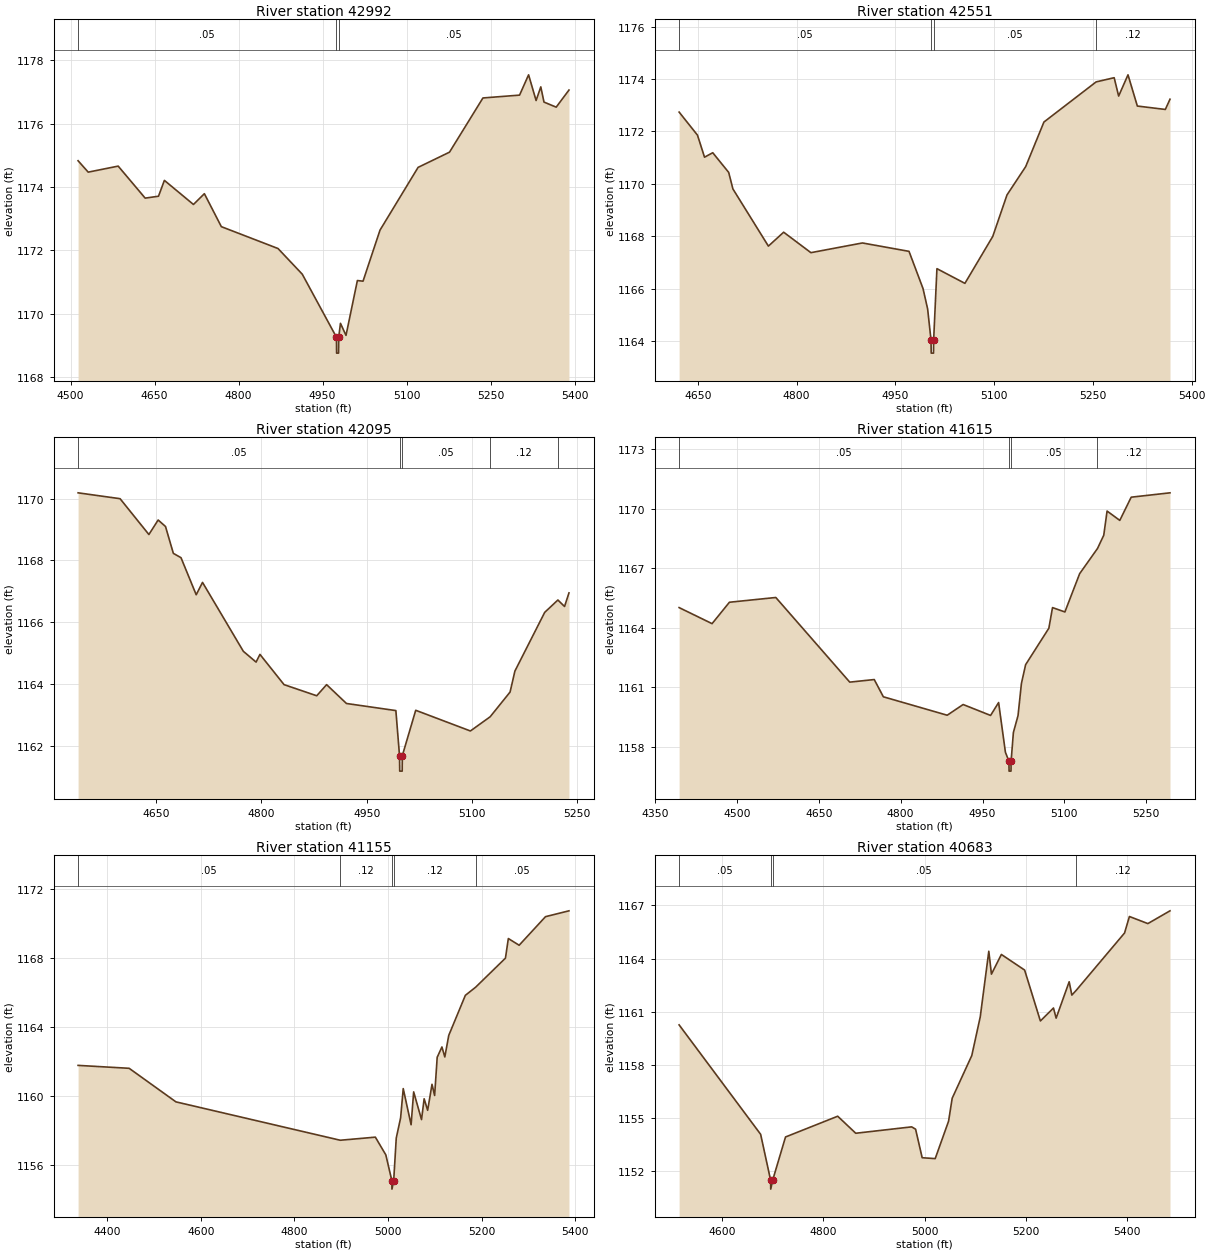
Type RM Length L Ch R = 1 ,42992   ,441,441,441
BEGIN DESCRIPTION:
Mapping XS c77aefb8
END DESCRIPTION:
XS GIS Cut Line= 4
      2871966.98     10279396.12      2871907.28     10279249.16
      2871838.41     10278803.77      2871604.19     10278675.18
#Sta/Elev= 30
  4513.5 1174.83  4531.6 1174.47  4585.1 1174.66  4633.3 1173.65  4657.1 1173.71
  4667.6 1174.21  4719.5 1173.45    4739 1173.79  4769.3 1172.75  4870.5 1172.06
  4913.8 1171.25  4974.9 1169.26  4975.1 1168.76  4978.6 1168.76  4978.9 1169.26
    4982  1169.7  4991.9 1169.32  5012.2 1171.05  5022.3 1171.03  5052.6 1172.64
  5120.6 1174.62  5176.7  1175.1  5236.4 1176.81  5301.8  1176.9  5317.9 1177.54
  5331.3 1176.73  5339.7 1177.16  5345.4 1176.68  5367.2 1176.52    5390 1177.06
#Mann= 3 ,-1 , 0
  4513.5     .05       0  4974.9     .03       0  4978.9     .05       0
Bank Sta=4974.9,4978.9
XS Rating Curve= 0 ,0
Exp/Cntr=0.3,0.1

Type RM Length L Ch R = 1 ,42551   ,456,456,456
BEGIN DESCRIPTION:
Mapping XS 495403d9
END DESCRIPTION:
XS GIS Cut Line= 4
      2872458.28     10279138.97      2872375.63     10278932.34
      2872214.92     10278776.22      2871994.51     10278574.18
#Sta/Elev= 30
  4621.5 1172.74  4649.4 1171.86  4660.1 1171.02  4672.6 1171.19  4696.8 1170.44
  4703.2 1169.81  4757.1 1167.63  4780.3 1168.16  4821.7 1167.38  4899.9 1167.75
  4970.7 1167.43    4992 1166.01    4999 1165.23  5004.1 1164.05  5004.4 1163.55
  5007.9 1163.55  5008.1 1164.05  5013.1 1166.77  5055.6 1166.21  5097.9    1168
  5119.5 1169.58  5147.9 1170.66  5175.6 1172.36  5254.9 1173.89  5282.3 1174.05
  5289.1 1173.35  5303.3 1174.16  5317.5 1172.97    5360 1172.84  5367.1 1173.23
#Mann= 4 ,-1 , 0
  4621.5     .05       0  5004.1     .05       0  5008.1     .05       0
  5254.9     .12       0
Bank Sta=5004.1,5008.1
XS Rating Curve= 0 ,0
Exp/Cntr=0.3,0.1

Type RM Length L Ch R = 1 ,42095   ,480,480,480
BEGIN DESCRIPTION:
Mapping XS d142bcbe
END DESCRIPTION:
XS GIS Cut Line= 3
      2872761.32     10278978.24      2872646.54     10278707.35
      2872366.43     10278413.46
#Sta/Elev= 30
  4538.4 1170.19  4598.3    1170  4639.4 1168.84  4652.6 1169.31  4663.1  1169.1
  4674.3 1168.23  4685.2 1168.09  4706.9 1166.89  4715.9 1167.29  4774.1 1165.06
  4792.3 1164.71  4797.8 1164.96  4832.2 1163.98  4878.8 1163.62  4892.9 1163.98
  4921.2 1163.37  4991.7 1163.14  4996.9 1161.68  4997.2 1161.18  5000.7 1161.18
  5000.9 1161.68    5020 1163.15    5098 1162.48  5126.2 1162.94  5154.6 1163.74
  5161.5 1164.42    5204 1166.32  5222.8 1166.72  5232.3 1166.51  5238.6 1166.95
#Mann= 5 ,-1 , 0
  4538.4     .05       0  4996.9     .05       0  5000.9     .05       0
  5126.2     .12       0  5222.8     .05       0
Bank Sta=4996.9,5000.9
XS Rating Curve= 0 ,0
Exp/Cntr=0.3,0.1

Type RM Length L Ch R = 1 ,41615   ,460,460,460
BEGIN DESCRIPTION:
Mapping XS 8bf73ddb
END DESCRIPTION:
XS GIS Cut Line= 3
      2872926.63     10278789.99      2872761.33     10278326.24
      2872431.16     10278087.79
#Sta/Elev= 30
    4394 1165.01  4454.4  1164.2  4486.2 1165.28  4571.2 1165.52  4706.7 1161.25
  4751.6 1161.38  4768.3 1160.51  4885.3 1159.58  4914.5 1160.12  4964.8 1159.57
  4979.5 1160.22    4992 1157.71  4998.4 1157.26  4998.7 1156.76  5002.2 1156.76
  5002.4 1157.26  5006.6 1158.71  5015.1 1159.56  5021.3 1161.18    5029 1162.13
  5071.6 1163.97  5078.3 1165.01    5101 1164.79    5128 1166.72  5160.7 1167.99
  5172.2 1168.66  5178.3 1169.88  5201.6 1169.41  5222.5 1170.58  5293.6  1170.8
#Mann= 4 ,-1 , 0
    4394     .05       0  4998.4     .05       0  5002.4     .05       0
  5160.7     .12       0
Bank Sta=4998.4,5002.4
XS Rating Curve= 0 ,0
Exp/Cntr=0.3,0.1

Type RM Length L Ch R = 1 ,41155   ,472,472,472
BEGIN DESCRIPTION:
Mapping XS 959782ca
END DESCRIPTION:
XS GIS Cut Line= 4
      2873032.23     10278652.21      2873013.87     10278137.98
      2872784.29     10278023.19      2872560.12      10277858.5
#Sta/Elev= 30
  4337.5 1161.77  4446.7  1161.6  4546.7 1159.65    4898 1157.42    4973  1157.6
  4995.4 1156.57  5008.2 1155.08  5008.5 1154.58  5012.2 1155.08  5017.7 1157.55
    5027 1158.72  5032.6 1160.42  5049.4 1158.32  5054.9 1160.23  5071.7 1158.62
  5077.3 1159.83  5084.8 1159.16  5094.1 1160.67  5099.7 1160.02  5105.2 1162.24
  5115.3 1162.84  5121.5 1162.26  5129.9 1163.51  5165.4 1165.84  5187.3 1166.31
  5251.1    1168  5257.3 1169.14  5280.4 1168.75  5336.7 1170.41  5386.9 1170.75
#Mann= 5 ,-1 , 0
  4337.5     .05       0    4898     .12       0  5008.2     .07       0
  5012.2     .12       0  5187.3     .05       0
Bank Sta=5008.2,5012.2
XS Rating Curve= 0 ,0
Exp/Cntr=0.3,0.1

Type RM Length L Ch R = 1 ,40683   ,577,577,577
BEGIN DESCRIPTION:
Mapping XS 153862b4
END DESCRIPTION:
XS GIS Cut Line= 5
      2873587.86     10278239.02      2873344.47     10278101.25
      2873280.18     10278000.23      2873206.72     10277747.69
      2873105.71     10277458.45
#Sta/Elev= 30
  4515.3 1160.26  4676.2 1154.09  4695.9  1151.5  4696.1    1151  4699.9  1151.5
  4725.3 1153.94  4828.3 1155.11  4863.9 1154.15  4974.2 1154.51    4982 1154.38
    4995 1152.77  5020.7 1152.72  5047.1 1154.83  5054.2 1156.12  5092.9 1158.53
  5109.6 1160.71  5126.5 1164.41  5131.7 1163.12  5151.3 1164.23  5197.2 1163.35
  5228.3 1160.48  5254.1 1161.21  5259.4 1160.64  5285.1 1162.69  5290.4 1161.94
  5298.5 1162.19  5394.4 1165.44    5404 1166.37  5440.4 1165.97  5484.1 1166.69
#Mann= 4 ,-1 , 0
  4515.3     .05       0  4695.9     .05       0  4699.9     .05       0
  5298.5     .12       0
Bank Sta=4695.9,4699.9
XS Rating Curve= 0 ,0
Exp/Cntr=0.3,0.1

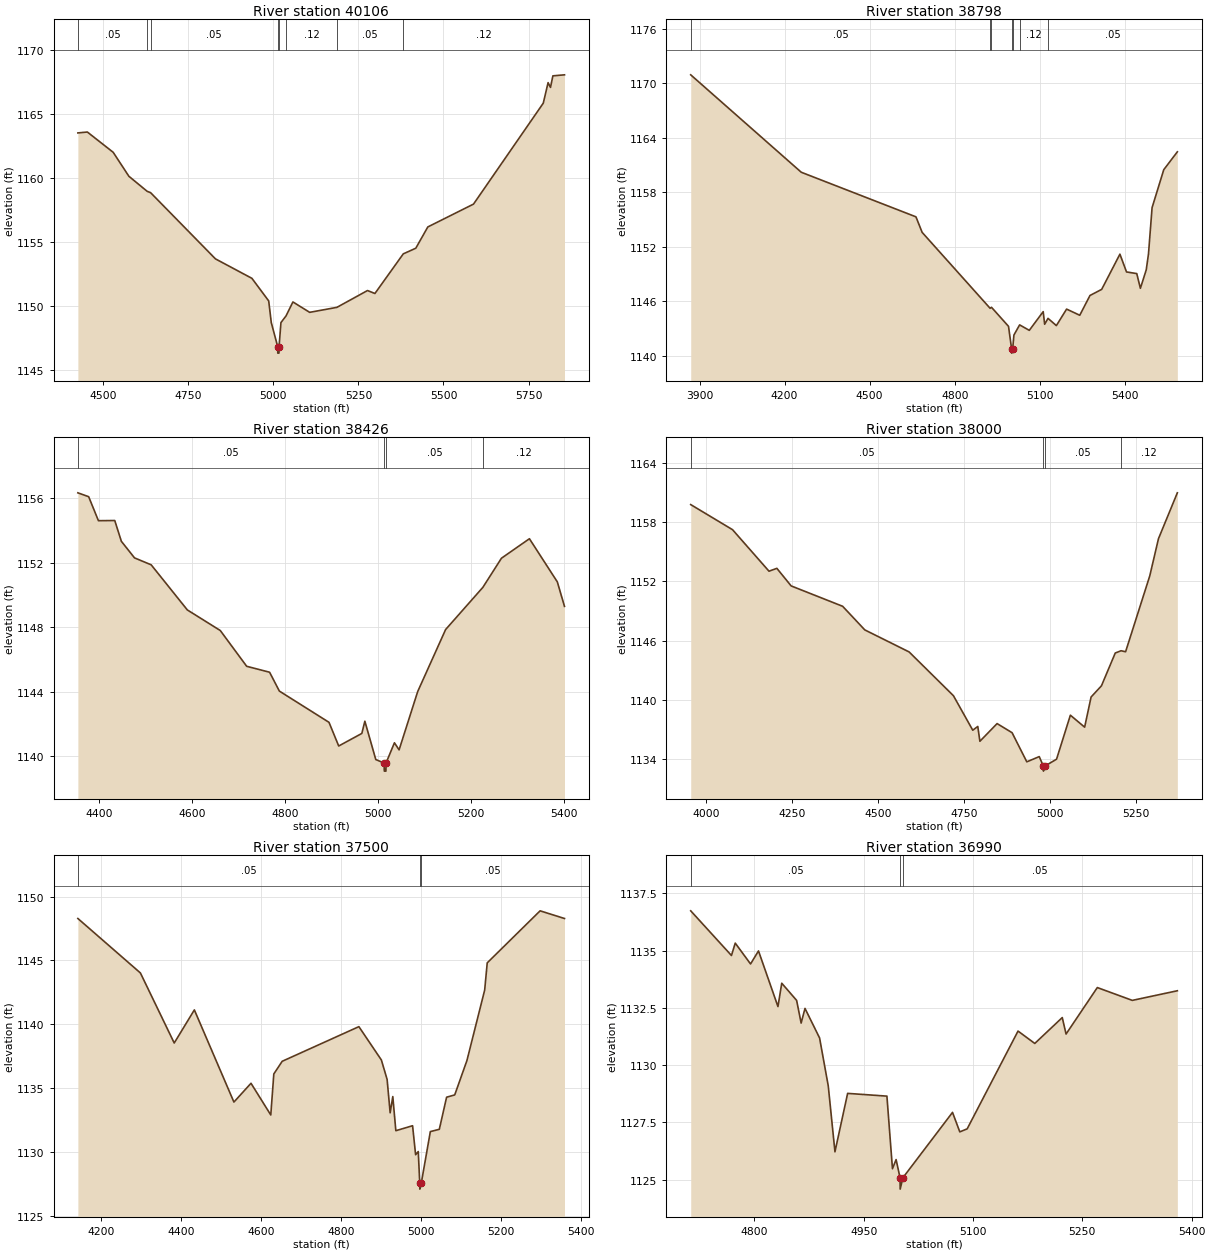
Type RM Length L Ch R = 1 ,40106   ,1308,1308,1308
BEGIN DESCRIPTION:
Mapping XS a9b90c1f
END DESCRIPTION:
XS GIS Cut Line= 5
      2873900.07     10278110.48        2873822.     10277701.78
      2873592.42     10277499.74      2873430.35     10277312.74
      2873102.71     10276987.82
#Sta/Elev= 30
    4425 1163.52  4452.9 1163.59  4528.8 1162.01    4575 1160.14  4628.6 1158.97
  4638.9 1158.86  4829.5  1153.7  4936.8 1152.18  4986.1 1150.42  4993.7 1148.73
  5012.6 1146.85  5012.8 1146.35  5016.3 1146.35  5016.6 1146.85  5022.1 1148.73
    5037 1149.25  5057.3 1150.34  5106.6 1149.53  5186.7 1149.92  5276.6 1151.23
  5298.4    1151  5381.8 1154.09  5418.6 1154.53    5454 1156.19  5588.3 1157.97
  5793.4 1165.84  5807.6 1167.44  5814.6 1167.07  5821.7 1167.97  5855.8 1168.05
#Mann= 8 ,-1 , 0
    4425     .05       0  4628.6     .12       0  4638.9     .05       0
  5012.6     .05       0  5016.6     .05       0    5037     .12       0
  5186.7     .05       0  5381.8     .12       0
Bank Sta=5012.6,5016.6
XS Rating Curve= 0 ,0
Exp/Cntr=0.3,0.1

Type RM Length L Ch R = 1 ,38798   ,372,372,372
BEGIN DESCRIPTION:
CAMPGROUND CREEK 77.0
END DESCRIPTION:
XS GIS Cut Line= 3
      2874055.69      10278503.1      2874505.68     10277453.11
       2874644.7     10276896.67
#Sta/Elev= 30
    3869 1170.92  4258.8 1160.19  4663.2 1155.28    4685 1153.57  4924.6 1145.21
  4929.5 1145.32  4989.6 1143.22  5000.3 1140.77  5000.5 1140.27  5004.3 1140.77
  5008.6 1142.26  5028.8 1143.38  5062.9 1142.78  5111.9 1144.84    5117 1143.45
  5128.9  1144.1  5158.3  1143.3  5194.4 1145.12  5240.8 1144.44  5276.9 1146.62
  5318.1 1147.29  5382.4 1151.17  5405.7 1149.21  5441.8 1149.03  5454.6 1147.41
  5475.2 1149.44  5483.1 1151.18  5495.8 1156.29    5537 1160.47  5584.9 1162.44
#Mann= 7 ,-1 , 0
    3869     .05       0  4924.6     .12       0  4929.5     .05       0
  5000.3     .05       0  5004.3     .05       0  5028.8     .12       0
  5128.9     .05       0
Bank Sta=5000.3,5004.3
XS Rating Curve= 0 ,0
Exp/Cntr=0.3,0.1

Type RM Length L Ch R = 1 ,38426   ,426,426,426
BEGIN DESCRIPTION:
Mapping XS b722e28a
END DESCRIPTION:
XS GIS Cut Line= 3
      2874441.55     10277991.43       2874832.2     10277566.06
      2874814.86     10277097.72
#Sta/Elev= 30
  4354.3 1156.34  4377.5  1156.1  4398.5 1154.61  4433.6 1154.62  4447.8 1153.33
  4476.1  1152.3  4511.9 1151.87  4589.6 1149.07  4660.5 1147.79  4717.2 1145.57
  4766.5  1145.2  4787.5 1144.03  4894.2 1142.09  4915.1 1140.62  4964.8  1141.4
  4971.3 1142.16  4994.8 1139.78  5012.8 1139.56  5013.1 1139.06  5016.6 1139.06
  5016.8 1139.56  5034.9 1140.82  5044.9 1140.38  5084.9    1144  5144.9 1147.85
    5225 1150.47    5265 1152.28  5325.1 1153.49  5385.1 1150.81  5400.5 1149.29
#Mann= 4 ,-1 , 0
  4354.3     .05       0  5012.8     .05       0  5016.8     .05       0
    5225     .12       0
Bank Sta=5012.8,5016.8
XS Rating Curve= 0 ,0
Exp/Cntr=0.3,0.1

Type RM Length L Ch R = 1 ,38000   ,500,500,500
BEGIN DESCRIPTION:
CAMPGROUND CREEK 76.0
END DESCRIPTION:
XS GIS Cut Line= 3
      2874355.71     10278203.09      2875189.56     10277572.07
      2875155.69     10277203.12
#Sta/Elev= 30
  3954.3 1159.76    4076 1157.22  4182.1 1153.02    4205 1153.31  4246.6 1151.53
  4396.4 1149.47  4460.9 1147.08  4589.9 1144.85  4718.9 1140.42  4775.1 1136.93
  4789.7 1137.31  4795.9 1135.81  4845.9  1137.6  4889.5 1136.68  4932.4 1133.73
  4968.6 1134.26  4980.6 1133.29  4980.8 1132.79  4984.6 1133.29    5019    1134
  5059.2 1138.45  5100.7 1137.24  5119.5 1140.29  5149.6 1141.42  5189.8 1144.74
  5206.7 1144.97  5219.9 1144.87  5290.2 1152.54  5315.6 1156.31  5370.5 1160.95
#Mann= 4 ,-1 , 0
  3954.3     .05       0  4980.6     .05       0  4984.6     .05       0
  5206.7     .12       0
Bank Sta=4980.6,4984.6
XS Rating Curve= 0 ,0
Exp/Cntr=0.3,0.1

Type RM Length L Ch R = 1 ,37500   ,510,510,510
BEGIN DESCRIPTION:
CAMPGROUND CREEK 75.0
END DESCRIPTION:
XS GIS Cut Line= 3
       2875005.7     10278453.09      2875568.08     10277805.63
      2875505.68     10277453.11
#Sta/Elev= 30
  4142.4 1148.28  4298.6 1144.02  4383.1 1138.54  4433.4 1141.13  4532.2 1133.92
  4574.9 1135.39  4624.3 1132.91  4631.9 1136.12  4652.8 1137.11  4844.4 1139.82
  4900.6 1137.21  4914.9 1135.69  4922.5 1133.08  4929.1 1134.35  4936.7 1131.68
  4978.5 1132.07  4986.1  1129.8  4992.7 1130.05  4996.4 1127.61  4996.6 1127.11
  5000.4 1127.61  5022.9 1131.61  5045.3 1131.79  5063.5  1134.3  5083.8 1134.48
  5114.3 1137.17  5158.6 1142.68    5165 1144.81  5297.1 1148.88    5358 1148.28
#Mann= 3 ,-1 , 0
  4142.4     .05       0  4996.4     .05       0  5000.4     .05       0
Bank Sta=4996.4,5000.4
XS Rating Curve= 0 ,0
Exp/Cntr=0.3,0.1

Type RM Length L Ch R = 1 ,36990   ,288,288,288
BEGIN DESCRIPTION:
Mapping XS 2450957b
END DESCRIPTION:
XS GIS Cut Line= 4
      2875873.33      10278271.2      2875942.79      10278058.5
       2875934.1     10277828.46      2875886.36     10277620.12
#Sta/Elev= 30
  4712.7 1136.74  4768.6 1134.79  4773.8 1135.33  4794.8 1134.42  4805.7 1134.99
  4832.4 1132.56  4837.6 1133.58    4858 1132.83  4864.2 1131.84  4869.5 1132.48
  4889.5 1131.19  4901.4  1129.1  4910.6 1126.22    4928 1128.77  4981.9 1128.65
  4989.5 1125.48  4994.5 1125.88  4999.9 1125.09  5000.1 1124.59  5003.9 1125.09
  5071.9 1127.94  5081.9 1127.09    5092 1127.22  5161.8 1131.49  5184.8 1130.95
  5222.5 1132.08  5227.7 1131.36  5270.6 1133.39  5318.6 1132.83  5380.4 1133.25
#Mann= 3 ,-1 , 0
  4712.7     .05       0  4999.9     .05       0  5003.9     .05       0
#XS Ineff= 2 , 0
       0  4981.9                       0
Permanent Ineff=
       F       F
Bank Sta=4999.9,5003.9
XS Rating Curve= 0 ,0
Exp/Cntr=0.3,0.1

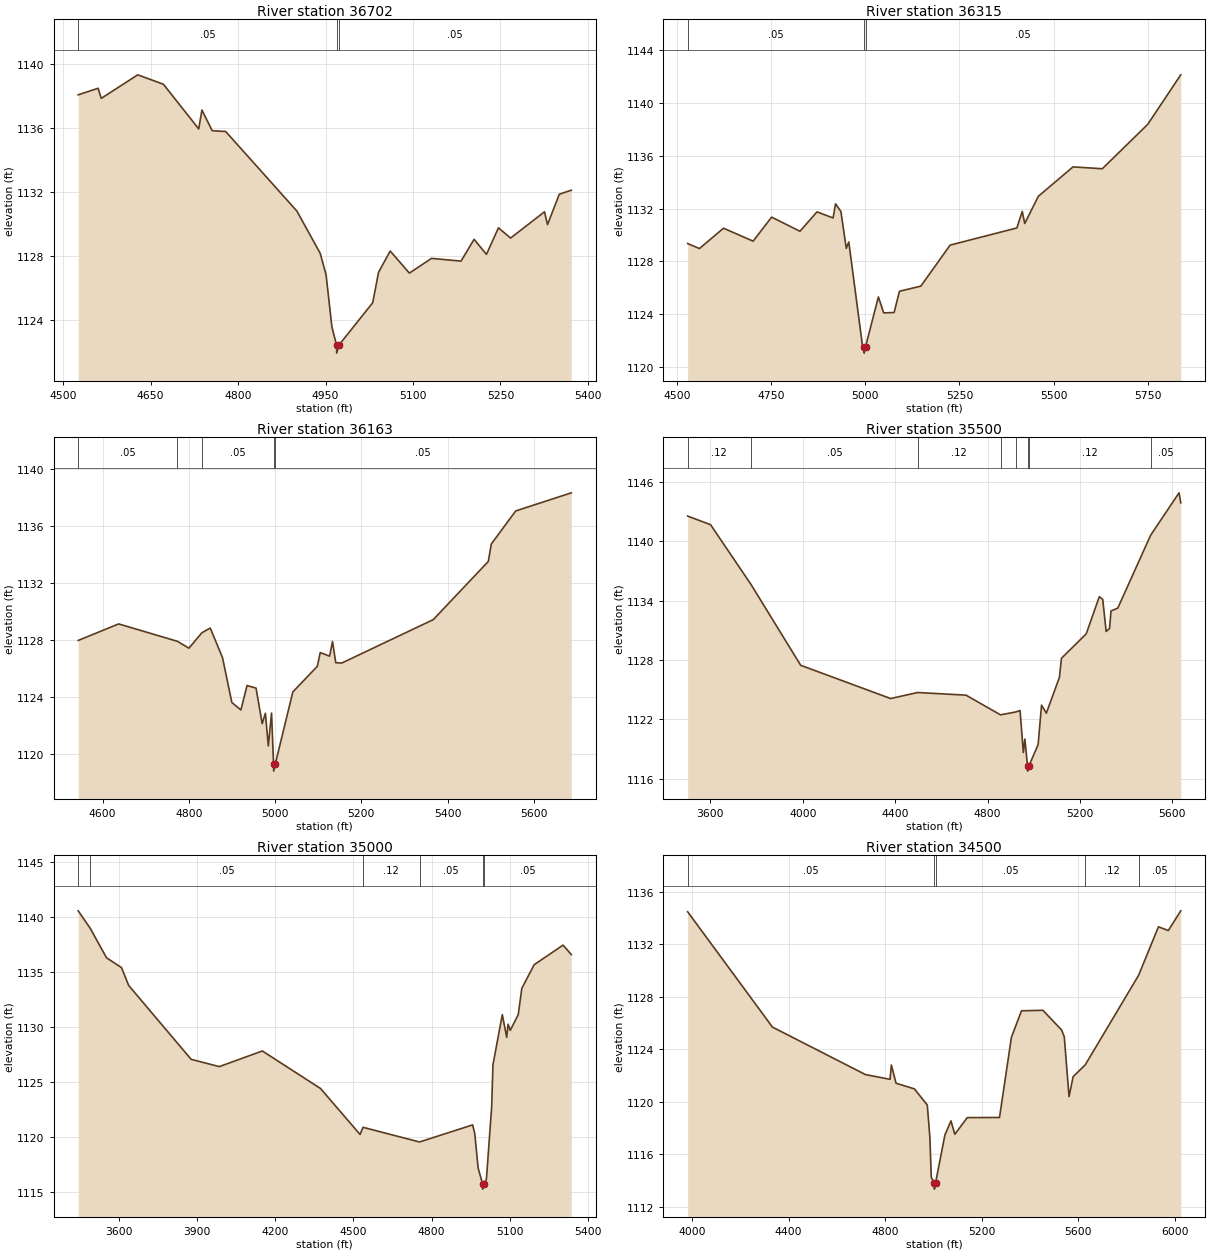
Type RM Length L Ch R = 1 ,36702   ,387,387,387
BEGIN DESCRIPTION:
Mapping XS 7d2b37cc
END DESCRIPTION:
XS GIS Cut Line= 4
      2876025.27     10278336.23      2876172.82     10278010.75
       2876181.5     10277780.72      2876107.72     10277533.35
#Sta/Elev= 30
  4525.8 1138.08  4559.9 1138.49  4565.4 1137.86    4628 1139.33    4672 1138.74
  4732.5 1135.95    4738 1137.13  4755.6 1135.84  4778.7 1135.79  4900.8 1130.82
  4940.8 1128.18  4950.9 1126.84  4960.9 1123.58  4968.9 1122.44  4969.1 1121.94
  4972.9 1122.44  5030.9 1125.09  5040.9 1126.99  5060.9 1128.32  5093.8 1126.94
  5131.7 1127.86  5182.4 1127.69  5204.8 1129.05    5226 1128.11  5246.5 1129.77
  5267.4 1129.13  5325.5 1130.77  5330.7 1129.97  5350.9 1131.87  5371.5 1132.12
#Mann= 3 ,-1 , 0
  4525.8     .05       0  4968.9     .03       0  4972.9     .05       0
Bank Sta=4968.9,4972.9
XS Rating Curve= 0 ,0
Exp/Cntr=0.3,0.1

Type RM Length L Ch R = 1 ,36315   ,152,152,152
BEGIN DESCRIPTION:
Mapping XS fb408f8e
END DESCRIPTION:
XS GIS Cut Line= 4
      2876828.17     10278145.27      2876632.89     10277919.61
      2876311.71     10277559.36      2875912.42     10277212.15
#Sta/Elev= 30
  4527.9 1129.35  4559.2 1128.97  4623.3 1130.51  4701.8 1129.53  4751.1 1131.35
  4826.3 1130.28  4871.6 1131.75  4914.3 1131.29    4921 1132.36  4935.2 1131.77
  4949.4 1128.98  4956.1 1129.47    4992 1121.69  4996.7 1121.54    4997 1121.04
  5000.7 1121.54  5034.7  1125.3  5048.9 1124.09  5076.5 1124.12  5090.7 1125.73
  5147.5 1126.12  5225.3 1129.23  5402.7 1130.53  5416.9 1131.78  5423.6 1130.87
  5459.7 1132.93  5551.8 1135.16  5629.6 1135.02  5750.2 1138.38  5838.1 1142.14
#Mann= 3 ,-1 , 0
  4527.9     .05       0  4996.7     .03       0  5000.7     .05       0
Bank Sta=4996.7,5000.7
XS Rating Curve= 0 ,0
Exp/Cntr=0.3,0.1

Type RM Length L Ch R = 1 ,36163   ,663,663,663
BEGIN DESCRIPTION:
Mapping XS 7e4a8126
END DESCRIPTION:
XS GIS Cut Line= 3
      2876910.68     10278010.76      2876463.62     10277507.28
      2876116.37     10277190.42
#Sta/Elev= 30
  4543.5 1127.98  4637.3 1129.14  4773.6 1127.92  4800.3 1127.44  4830.3 1128.52
  4849.7 1128.85  4878.1 1126.78  4899.8 1123.63  4920.8 1123.11    4935 1124.82
  4955.9 1124.64  4970.1 1122.15  4977.6 1122.88  4984.3 1120.59  4991.8 1122.89
  4996.5 1119.32  4996.8 1118.82  5000.5 1119.32  5041.2 1124.37    5098 1126.17
  5104.7 1127.13  5126.5 1126.88  5133.2 1127.91  5140.7 1126.42  5154.9  1126.4
  5366.8 1129.44  5494.5 1133.52  5501.3 1134.74    5558 1137.06  5686.9 1138.33
#Mann= 5 ,-1 , 0
  4543.5     .05       0  4773.6     .12       0  4830.3     .05       0
  4996.5     .03       0  5000.5     .05       0
Bank Sta=4996.5,5000.5
XS Rating Curve= 0 ,0
Exp/Cntr=0.3,0.1

Type RM Length L Ch R = 1 ,35500   ,500,500,500
BEGIN DESCRIPTION:
CAMPGROUND CREEK 71.0
END DESCRIPTION:
XS GIS Cut Line= 3
       2877805.7     10278053.13       2876676.5      10277068.8
      2876155.66      10276703.1
#Sta/Elev= 30
    3502 1142.55  3601.2 1141.68  3776.4 1135.63  3991.4 1127.46  4380.6  1124.1
  4497.6 1124.71  4707.2 1124.44  4856.2 1122.45  4921.8 1122.74  4940.8 1122.89
    4955 1118.64  4961.7    1120  4973.2 1117.26  4973.6 1116.76  4978.6 1117.26
    5019 1119.44  5033.8 1123.43  5054.7 1122.62  5111.3 1126.25    5120 1128.17
  5227.2 1130.64  5283.9  1134.4  5298.7 1134.13  5313.5 1130.88  5328.3 1131.18
  5334.4 1132.95    5364 1133.25    5506 1140.61    5629  1144.9  5636.4 1143.89
#Mann= 8 ,-1 , 0
    3502     .12       0  3776.4     .05       0  4497.6     .12       0
  4856.2     .05       0  4921.8     .12       0  4973.2     .07       0
  4978.6     .12       0    5506     .05       0
Bank Sta=4973.2,4978.6
XS Rating Curve= 0 ,0
Exp/Cntr=0.3,0.1

Type RM Length L Ch R = 1 ,35000   ,500,500,500
BEGIN DESCRIPTION:
CAMPGROUND CREEK 70.0
END DESCRIPTION:
XS GIS Cut Line= 3
      2877705.69     10277903.13      2876835.41     10276614.47
      2876505.67     10276553.11
#Sta/Elev= 30
    3445 1140.54  3491.5 1138.94  3553.6 1136.28  3611.3 1135.38  3638.4 1133.77
  3878.1 1127.06    3986  1126.4  4150.9 1127.82  4374.2 1124.41  4525.5 1120.24
    4537 1120.89  4753.6 1119.56  4957.1 1121.11  4965.4  1120.3  4978.1  1117.2
  4995.1 1115.78  4995.5 1115.28  5000.5 1115.78  5009.9 1116.17    5030 1122.72
    5035 1126.56  5070.9 1131.12  5087.8 1129.05  5092.9 1130.25  5101.4 1129.69
    5132 1131.12  5145.6  1133.5    5193 1135.65  5303.9 1137.43  5335.4 1136.57
#Mann= 6 ,-1 , 0
    3445     .12       0  3491.5     .05       0    4537     .12       0
  4753.6     .05       0  4995.1     .03       0  5000.5     .05       0
Bank Sta=4995.1,5000.5
XS Rating Curve= 0 ,0
Exp/Cntr=0.3,0.1

Type RM Length L Ch R = 1 ,34500   ,500,500,500
BEGIN DESCRIPTION:
CAMPGROUND CREEK 69.0
END DESCRIPTION:
XS GIS Cut Line= 3
       2877605.7     10277753.14      2877247.73     10276799.41
      2877005.68     10275803.09
#Sta/Elev= 30
  3981.3 1134.49  4332.8  1125.7  4718.3 1122.08  4820.3 1121.72  4825.7 1122.81
  4845.2 1121.42  4921.3 1120.99  4974.7 1119.76  4985.4 1117.29  4991.2 1114.24
  5003.7 1113.85  5004.1 1113.35  5009.3 1113.85  5047.6 1117.47  5072.8 1118.55
  5088.8 1117.53  5140.3  1118.8    5274 1118.81  5323.4 1124.92  5365.1 1126.94
  5453.8 1126.98  5531.3 1125.48  5542.5 1124.96  5562.2  1120.4  5579.1 1121.92
  5629.3 1122.82  5850.7 1129.65  5932.7 1133.34  5973.8 1133.06  6025.3 1134.56
#Mann= 5 ,-1 , 0
  3981.3     .05       0  5003.7     .05       0  5009.3     .05       0
  5629.3     .12       0  5850.7     .05       0
Bank Sta=5003.7,5009.3
XS Rating Curve= 0 ,0
Exp/Cntr=0.3,0.1