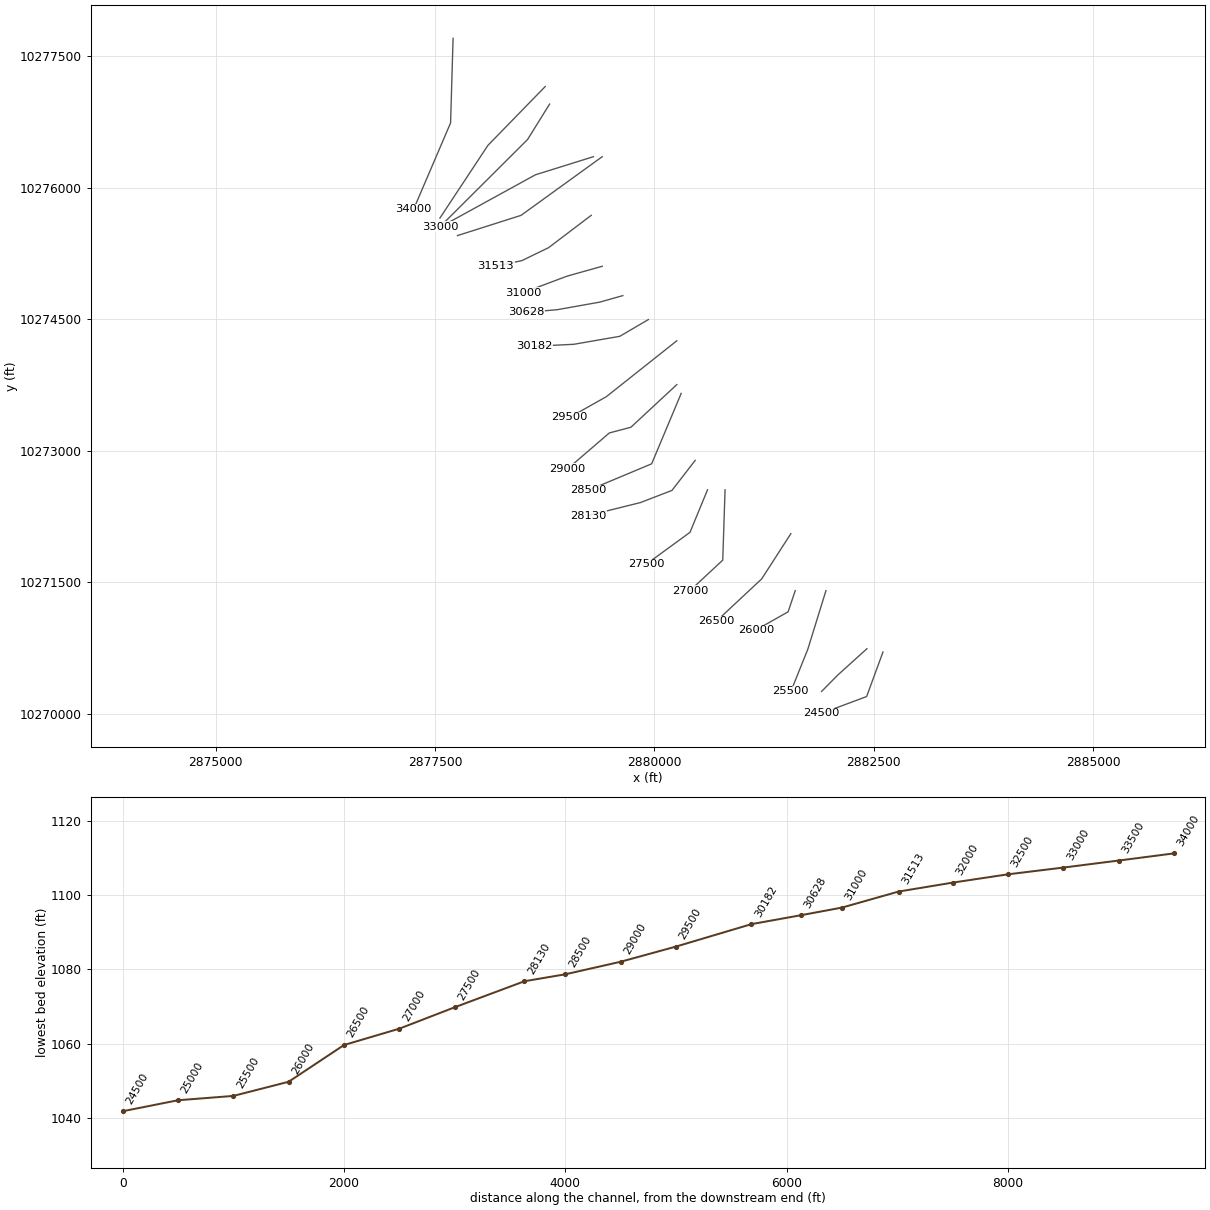
HEC-RAS study CAMPGROUND CREEK.prj: CAMPGROUND CREEK Base Level Engineering

--- CAMPGROUND CREEK.g01 (geometry) --- (continued)

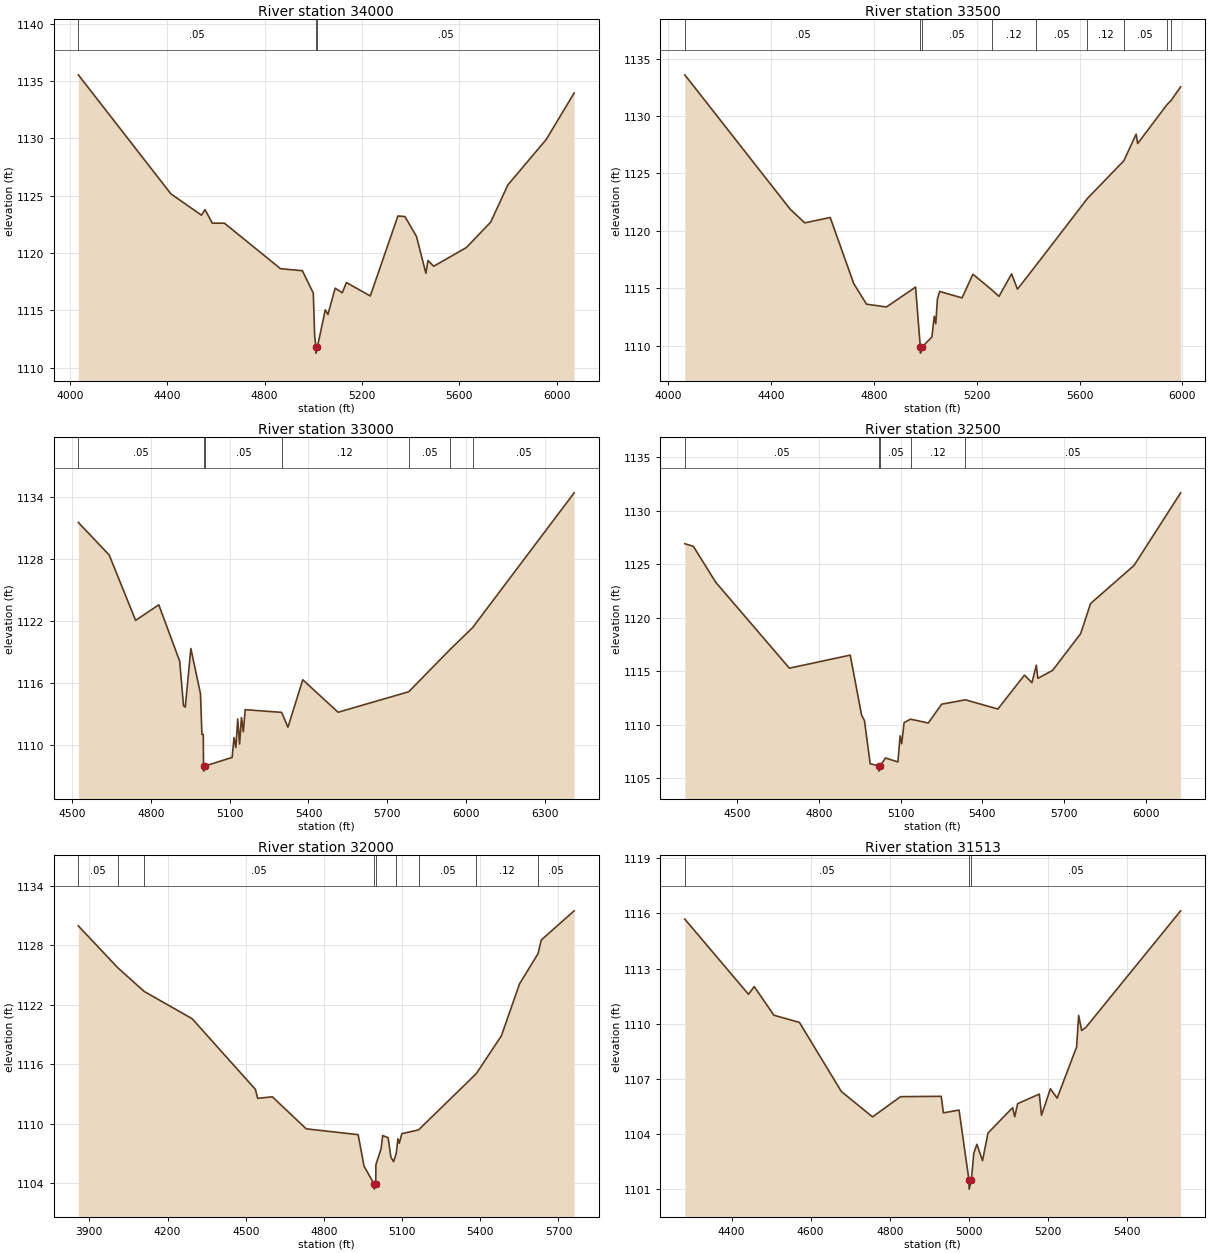
Type RM Length L Ch R = 1 ,34000   ,500,500,500
BEGIN DESCRIPTION:
CAMPGROUND CREEK 68.0
END DESCRIPTION:
XS GIS Cut Line= 3
      2877705.68     10277703.13      2877677.09     10276738.35
      2877255.68     10275753.09
#Sta/Elev= 30
  4034.8 1135.53    4415 1125.16  4540.6  1123.3    4555 1123.79  4585.1 1122.61
  4635.1  1122.6  4865.2 1118.64  4955.2 1118.46    5000 1116.51  5005.7 1112.75
  5010.9 1111.78  5011.4 1111.28  5016.5 1111.78  5049.2 1115.05  5060.1 1114.65
  5089.9 1116.94    5119 1116.54  5136.2 1117.43  5234.1 1116.26  5347.6 1123.23
  5376.6 1123.18  5423.8 1121.45  5462.5 1118.24    5471 1119.35  5494.6 1118.85
  5628.8 1120.48  5728.6 1122.69  5799.4 1125.94  5957.3 1129.91  6071.6 1133.95
#Mann= 3 ,-1 , 0
  4034.8     .05       0  5010.9     .03       0  5016.5     .05       0
Bank Sta=5010.9,5016.5
XS Rating Curve= 0 ,0
Exp/Cntr=0.3,0.1

Type RM Length L Ch R = 1 ,33500   ,500,500,500
BEGIN DESCRIPTION:
CAMPGROUND CREEK 67.0
END DESCRIPTION:
XS GIS Cut Line= 3
      2878755.71     10277153.13       2878102.6     10276482.09
       2877555.7     10275653.14
#Sta/Elev= 30
  4063.6 1133.58  4473.8 1121.88  4530.4 1120.69  4629.4 1121.16  4721.2  1115.4
  4770.8 1113.61  4848.5 1113.37  4961.7  1115.1  4980.2 1109.85  4980.7 1109.35
  4985.8 1109.85  5025.2 1110.76  5034.3 1112.56  5040.3 1111.91  5046.7 1114.06
  5055.3 1114.72  5142.5 1114.16  5184.8 1116.22  5258.3 1114.86  5286.3 1114.29
  5335.3 1116.25  5358.2 1114.92    5432 1117.04  5629.8  1122.8  5772.1  1126.1
    5820 1128.41    5826  1127.6  5938.8 1130.95  5956.2 1131.36  5993.1 1132.53
#Mann= 9 ,-1 , 0
  4063.6     .05       0  4980.2     .03       0  4985.8     .05       0
  5258.3     .12       0    5432     .05       0  5629.8     .12       0
  5772.1     .05       0  5938.8     .12       0  5956.2     .05       0
Bank Sta=4980.2,4985.8
XS Rating Curve= 0 ,0
Exp/Cntr=0.3,0.1

Type RM Length L Ch R = 1 ,33000   ,500,500,500
BEGIN DESCRIPTION:
CAMPGROUND CREEK 66.0
END DESCRIPTION:
XS GIS Cut Line= 3
      2878805.68     10276953.11      2878554.88     10276549.25
      2877555.69     10275553.12
#Sta/Elev= 30
  4524.6 1131.58  4642.1 1128.42  4742.5 1122.08  4830.7 1123.59  4910.2 1118.12
  4924.8 1113.79  4931.4 1113.67  4952.7 1119.35  4989.3 1114.97  4994.8 1111.02
    5000 1111.02  5000.9 1107.96  5001.4 1107.46  5006.7 1107.96  5109.8 1108.79
  5116.9 1110.72    5124 1109.75    5131 1112.52  5138.1 1110.09  5145.2 1112.66
  5152.3 1111.28  5159.3 1113.42  5298.1 1113.16    5322 1111.72  5378.5 1116.32
  5512.9 1113.17  5781.6 1115.16    5939 1119.26  6024.6 1121.38  6410.9 1134.45
#Mann= 7 ,-1 , 0
  4524.6     .05       0  5000.9     .03       0  5006.7     .05       0
  5298.1     .12       0  5781.6     .05       0    5939     .12       0
  6024.6     .05       0
Bank Sta=5000.9,5006.7
XS Rating Curve= 0 ,0
Exp/Cntr=0.3,0.1

Type RM Length L Ch R = 1 ,32500   ,500,500,500
BEGIN DESCRIPTION:
CAMPGROUND CREEK 65.0
END DESCRIPTION:
XS GIS Cut Line= 3
      2879305.64      10276353.1      2878644.69     10276146.81
      2877655.68     10275603.11
#Sta/Elev= 30
  4307.6 1126.91    4339 1126.67  4421.3  1123.3  4691.7 1115.27  4915.2 1116.49
  4956.9 1110.88  4967.5 1110.36  4988.5 1106.33  5019.8 1106.14  5020.3 1105.64
  5025.6 1106.14  5044.5 1106.87  5090.2  1106.5  5098.5 1108.94  5104.2 1108.21
    5113 1110.18  5136.8  1110.5  5201.7 1110.14    5251  1111.9    5338 1112.31
  5457.5 1111.45    5555 1114.62  5582.5 1113.91  5598.6 1115.55  5604.3 1114.32
  5658.3 1115.06  5761.5  1118.5  5797.7 1121.31  5957.6 1124.88  6128.6 1131.67
#Mann= 5 ,-1 , 0
  4307.6     .05       0  5019.8     .03       0  5025.6     .05       0
  5136.8     .12       0    5338     .05       0
Bank Sta=5019.8,5025.6
XS Rating Curve= 0 ,0
Exp/Cntr=0.3,0.1

Type RM Length L Ch R = 1 ,32000   ,487,487,487
BEGIN DESCRIPTION:
CAMPGROUND CREEK 64.0
END DESCRIPTION:
XS GIS Cut Line= 3
      2879405.67      10276353.1      2878480.11      10275683.8
      2877755.65      10275453.1
#Sta/Elev= 30
  3857.8 1129.98  4008.9 1125.76  4110.5 1123.36  4294.4 1120.61  4537.3 1113.47
  4545.8 1112.57  4602.3 1112.72  4732.2 1109.49  4931.4  1108.9  4954.2 1105.71
  4993.1  1103.9  4993.6  1103.4  4998.9  1103.9  4999.6 1105.87  5019.6 1107.49
  5025.6 1108.81  5046.5 1108.59  5057.1 1106.63  5067.6 1106.17  5077.9 1107.03
    5084 1108.49  5089.3 1108.03  5099.1    1109  5163.2 1109.38  5384.7 1115.06
  5481.1 1118.88  5550.8 1124.13  5621.5 1127.17  5634.3 1128.56  5760.3  1131.5
#Mann= 9 ,-1 , 0
  3857.8     .05       0  4008.9     .12       0  4110.5     .05       0
  4993.1     .03       0  4998.9     .05       0  5077.9     .12       0
  5163.2     .05       0  5384.7     .12       0  5621.5     .05       0
Bank Sta=4993.1,4998.9
XS Rating Curve= 0 ,0
Exp/Cntr=0.3,0.1

Type RM Length L Ch R = 1 ,31513   ,513,513,513
BEGIN DESCRIPTION:
Mapping XS 4e589776
END DESCRIPTION:
XS GIS Cut Line= 4
      2879280.45     10275684.36      2878794.35     10275315.44
      2878490.53     10275167.87      2878191.02     10275102.76
#Sta/Elev= 30
  4281.6 1115.69  4442.7  1111.6  4457.2 1112.02  4507.1 1110.46  4571.6 1110.07
  4677.7 1106.31  4756.7 1104.93  4827.5 1106.03  4930.4 1106.05  4935.9 1105.15
  4975.5  1105.3  5000.5  1101.5    5001    1101  5006.8  1101.5  5012.6 1102.94
  5020.6 1103.44  5034.9 1102.55  5048.7 1104.05  5110.9 1105.43  5116.4 1104.94
  5123.8 1105.65  5178.6 1106.17  5184.1 1105.02  5206.7 1106.46  5223.7 1105.95
    5273 1108.74  5278.1 1110.45  5285.7 1109.63    5296 1109.79  5536.1 1116.14
#Mann= 3 ,-1 , 0
  4281.6     .05       0  5000.5     .03       0  5006.8     .05       0
Bank Sta=5000.5,5006.8
XS Rating Curve= 0 ,0
Exp/Cntr=0.3,0.1

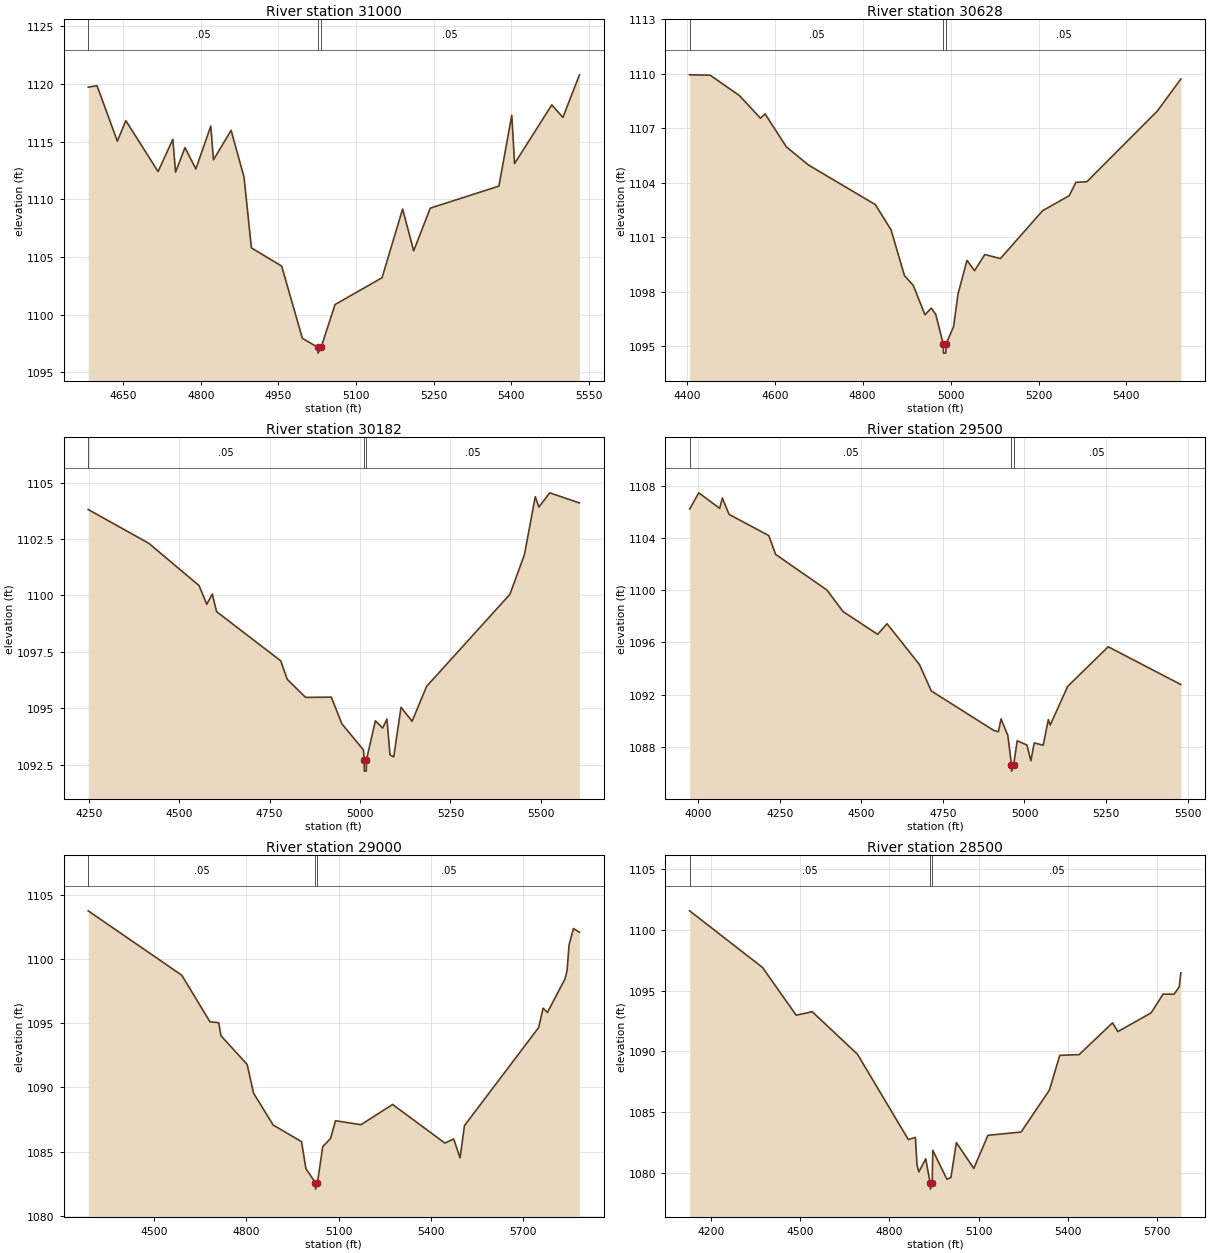
Type RM Length L Ch R = 1 ,31000   ,372,372,372
BEGIN DESCRIPTION:
CAMPGROUND CREEK 62.0
END DESCRIPTION:
XS GIS Cut Line= 3
      2879405.66     10275103.11      2879003.65     10274990.09
      2878505.69     10274803.11
#Sta/Elev= 30
  4582.4 1119.71  4599.4 1119.84  4638.7 1115.03  4655.1 1116.81  4717.4  1112.4
    4746 1115.19  4751.2 1112.35  4769.4 1114.47  4790.5 1112.63  4819.3 1116.34
  4824.5 1113.42  4858.6 1115.97  4883.6 1111.91  4897.8 1105.79  4956.3 1104.21
  4996.3 1097.96  5026.1 1097.17  5026.6 1096.67  5032.5 1097.17  5059.5 1100.88
  5150.3  1103.2  5190.1 1109.15  5211.5 1105.53  5243.5 1109.23  5376.2 1111.14
  5401.1 1117.28  5406.5 1113.09  5478.5 1118.18  5499.9 1117.09  5531.9 1120.78
#Mann= 3 ,-1 , 0
  4582.4     .05       0  5026.1     .03       0  5032.5     .05       0
Bank Sta=5026.1,5032.5
XS Rating Curve= 0 ,0
Exp/Cntr=0.3,0.1

Type RM Length L Ch R = 1 ,30628   ,446,446,446
BEGIN DESCRIPTION:
Mapping XS a99cd727
END DESCRIPTION:
XS GIS Cut Line= 4
      2879640.74     10274768.58      2879380.29     10274694.78
      2878894.17     10274607.98      2878542.59     10274577.59
#Sta/Elev= 30
  4406.4 1109.94  4453.2 1109.92  4519.5  1108.8  4567.6 1107.55    4578 1107.79
  4626.5 1105.97  4676.9 1104.97  4828.9 1102.79  4864.6  1101.4  4895.1 1098.88
  4915.4 1098.33  4941.7 1096.72    4956 1097.09  4966.2 1096.75  4983.3 1095.11
  4983.8 1094.61  4989.2 1094.61  4989.7 1095.11  5006.8 1096.07    5017 1097.88
  5037.3 1099.72  5054.5 1099.15  5077.9 1100.04  5113.4 1099.82  5209.5 1102.46
  5269.8 1103.28  5285.1 1104.02  5309.9 1104.05  5470.5 1107.95  5523.8 1109.71
#Mann= 3 ,-1 , 0
  4406.4     .05       0  4983.3     .03       0  4989.7     .05       0
Bank Sta=4983.3,4989.7
XS Rating Curve= 0 ,0
Exp/Cntr=0.3,0.1

Type RM Length L Ch R = 1 ,30182   ,682,682,682
BEGIN DESCRIPTION:
Mapping XS beb15476
END DESCRIPTION:
XS GIS Cut Line= 4
      2879931.46      10274495.1      2879605.98     10274304.16
      2879080.81     10274213.01      2878633.71     10274191.31
#Sta/Elev= 30
  4248.7 1103.81  4416.3 1102.31    4555 1100.44  4576.5 1099.61  4591.6 1100.06
  4603.7 1099.28    4781  1097.1  4798.9 1096.28  4849.6 1095.48  4920.7 1095.49
  4949.9 1094.31  5009.6 1093.15  5011.5 1092.71    5012 1092.21  5017.4 1092.21
  5017.9 1092.71  5042.5 1094.44  5062.8 1094.12  5074.4 1094.52  5083.1 1092.93
  5093.2 1092.84  5113.5 1095.04    5144 1094.42  5184.2 1095.97  5414.5 1100.05
  5454.6 1101.81  5484.6 1104.38  5494.6 1103.92  5524.6 1104.55  5606.7  1104.1
#Mann= 3 ,-1 , 0
  4248.7     .05       0  5011.5     .03       0  5017.9     .05       0
Bank Sta=5011.5,5017.9
XS Rating Curve= 0 ,0
Exp/Cntr=0.3,0.1

Type RM Length L Ch R = 1 ,29500   ,500,500,500
BEGIN DESCRIPTION:
CAMPGROUND CREEK 59.0
END DESCRIPTION:
XS GIS Cut Line= 3
      2880255.71     10274253.13      2879452.15     10273615.36
       2879034.8     10273379.87
#Sta/Elev= 30
  3974.1  1106.2  4002.2 1107.44  4066.2 1106.25  4074.3 1107.04  4095.1 1105.79
  4216.7 1104.17  4237.7 1102.73  4394.7 1100.01  4444.4 1098.36  4550.1 1096.62
    4579 1097.43  4678.3 1094.31  4714.6 1092.29  4906.1 1089.27  4920.2 1089.17
  4928.2 1090.15  4949.1 1088.89  4960.2 1086.66  4960.7 1086.16  4966.8 1086.66
  4977.9 1088.48  5007.4 1088.16  5019.7 1086.95  5029.9 1088.32  5057.3 1088.14
  5073.2  1090.1  5078.9 1089.68  5132.4 1092.64  5256.6 1095.67  5479.2 1092.78
#Mann= 3 ,-1 , 0
  3974.1     .05       0  4960.2     .05       0  4966.8     .05       0
Bank Sta=4960.2,4966.8
XS Rating Curve= 0 ,0
Exp/Cntr=0.3,0.1

Type RM Length L Ch R = 1 ,29000   ,500,500,500
BEGIN DESCRIPTION:
CAMPGROUND CREEK 58.0
END DESCRIPTION:
XS GIS Cut Line= 4
      2880255.71     10273753.13      2879732.38     10273266.82
      2879486.68     10273201.91      2879009.95     10272791.93
#Sta/Elev= 30
  4285.6 1103.76  4589.8 1098.74  4681.6 1095.11    4710 1095.04  4717.3 1094.02
  4802.3 1091.79  4823.3 1089.55  4886.8 1087.07  4979.2 1085.77  4993.4 1083.67
  5024.3 1082.57  5024.8 1082.07  5030.9 1082.57  5048.3 1085.39  5073.7 1086.02
  5089.7  1087.4  5172.4 1087.09  5275.3 1088.67  5445.3 1085.66  5473.9 1085.98
  5494.7 1084.51    5509 1087.02  5750.4 1094.67  5764.6 1096.17  5778.9 1095.84
  5835.8 1098.45  5842.6 1099.08  5849.2 1101.11  5863.4 1102.38  5882.9 1102.09
#Mann= 3 ,-1 , 0
  4285.6     .05       0  5024.3     .03       0  5030.9     .05       0
Bank Sta=5024.3,5030.9
XS Rating Curve= 0 ,0
Exp/Cntr=0.3,0.1

Type RM Length L Ch R = 1 ,28500   ,370,370,370
BEGIN DESCRIPTION:
CAMPGROUND CREEK 57.0
END DESCRIPTION:
XS GIS Cut Line= 3
      2880305.68      10273653.1       2879968.9     10272849.62
      2879250.69     10272548.73
#Sta/Elev= 30
  4128.8 1101.55  4373.6  1096.9  4486.6 1092.98  4540.8 1093.26  4692.6 1089.77
  4863.4 1082.76  4887.1 1082.94  4892.6 1080.68  4898.6  1080.1  4921.8 1081.18
  4936.8 1079.19  4937.3 1078.69  4943.5 1079.19  4945.5 1081.88  4993.1  1079.5
  5006.4 1079.65  5024.8 1082.51  5083.2 1080.39  5130.7 1083.11  5242.1 1083.38
  5337.3 1086.83  5372.1 1089.68  5437.2 1089.74  5549.2 1092.35  5567.3 1091.63
    5679 1093.17  5719.1 1094.71  5755.7  1094.7  5773.3  1095.3  5778.7 1096.46
#Mann= 3 ,-1 , 0
  4128.8     .05       0  4936.8     .03       0  4943.5     .05       0
#XS Ineff= 2 , 0
       0                 5024.74       0
Permanent Ineff=
       F       F
Bank Sta=4936.8,4943.5
XS Rating Curve= 0 ,0
Exp/Cntr=0.3,0.1

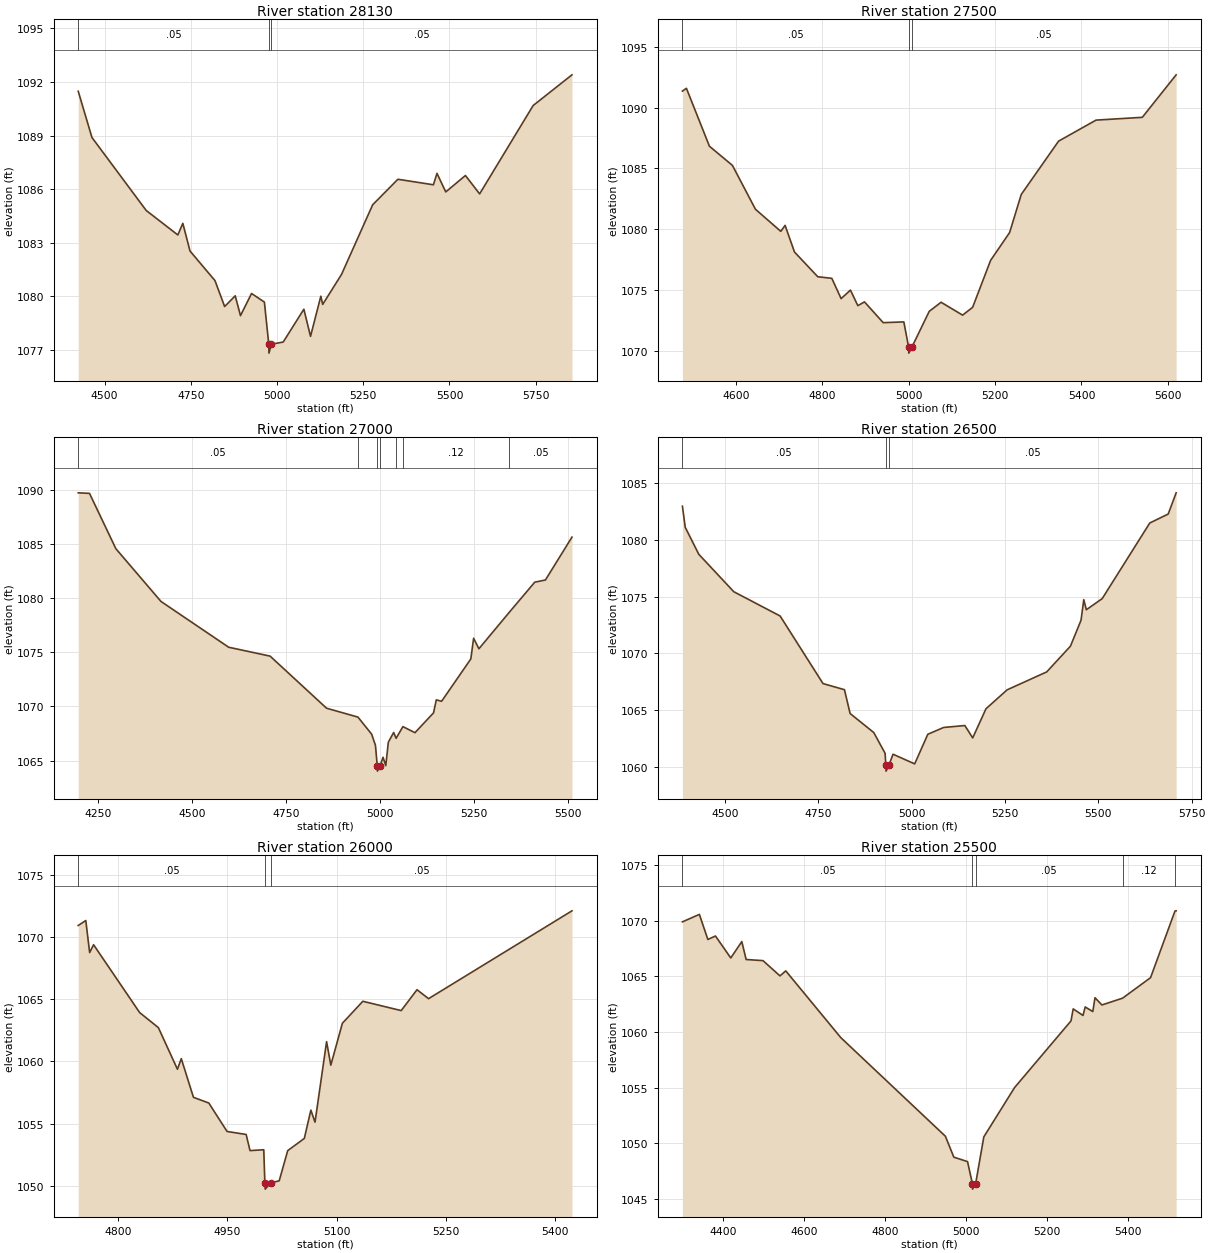
Type RM Length L Ch R = 1 ,28130   ,630,630,630
BEGIN DESCRIPTION:
Mapping XS e1dea201
END DESCRIPTION:
XS GIS Cut Line= 4
      2880465.34      10272889.2       2880200.6     10272546.34
      2879840.35     10272407.45      2879245.76     10272259.89
#Sta/Elev= 30
  4423.3 1091.48  4463.1 1088.89  4620.5  1084.8  4712.2 1083.43  4726.7 1084.08
  4747.5 1082.53    4820 1080.87  4847.9 1079.42  4878.6 1080.02  4893.9 1078.91
    4926 1080.15  4963.2 1079.67  4975.9 1077.31  4976.4 1076.81  4983.4 1077.31
  5017.7 1077.43  5077.7 1079.27    5097 1077.75  5126.9    1080  5132.3 1079.54
  5186.9 1081.22  5277.2 1085.12  5350.4 1086.55  5453.4 1086.24  5463.7 1086.88
  5489.2 1085.84  5546.2 1086.76  5587.4 1085.73  5742.6 1090.68  5855.2  1092.4
#Mann= 3 ,-1 , 0
  4423.3     .05       0  4975.9     .03       0  4983.4     .05       0
Bank Sta=4975.9,4983.4
XS Rating Curve= 0 ,0
Exp/Cntr=0.3,0.1

Type RM Length L Ch R = 1 ,27500   ,500,500,500
BEGIN DESCRIPTION:
CAMPGROUND CREEK 55.0
END DESCRIPTION:
XS GIS Cut Line= 3
       2880605.7     10272553.14      2880406.01     10272068.14
      2879905.71     10271703.13
#Sta/Elev= 30
  4475.5 1091.37  4484.8  1091.6  4538.1 1086.83  4591.4 1085.25  4644.7 1081.64
  4703.4 1079.82  4713.4 1080.31  4735.1 1078.12  4789.1 1076.08  4821.6 1075.95
  4843.2 1074.28  4864.8 1074.98  4881.9  1073.7  4897.3 1074.01  4940.6  1072.3
  4988.5 1072.36  4999.5 1070.29    5000 1069.79  5007.2 1070.29  5047.3 1073.23
  5074.7 1073.98  5124.6 1072.92  5147.8 1073.56  5189.5 1077.43  5233.5 1079.72
  5260.5 1082.86    5347 1087.25  5433.7 1088.98  5540.9 1089.21  5619.3 1092.71
#Mann= 3 ,-1 , 0
  4475.5     .05       0  4999.5     .05       0  5007.2     .05       0
Bank Sta=4999.5,5007.2
XS Rating Curve= 0 ,0
Exp/Cntr=0.3,0.1

Type RM Length L Ch R = 1 ,27000   ,500,500,500
BEGIN DESCRIPTION:
CAMPGROUND CREEK 54.0
END DESCRIPTION:
XS GIS Cut Line= 3
      2880805.68     10272553.14      2880779.25     10271750.87
      2880405.67      10271403.1
#Sta/Elev= 30
  4197.3 1089.73  4227.3 1089.68  4297.4 1084.57  4417.4  1079.7  4597.5 1075.47
  4707.6 1074.65  4857.7 1069.84  4941.2 1069.02  4977.7 1067.44  4987.8 1066.41
  4992.5 1064.53    4993 1064.03  5000.3 1064.53  5007.9 1065.31  5015.2 1064.54
    5022  1066.7  5036.2  1067.6  5042.7 1067.06  5060.8 1068.14  5092.9 1067.58
  5142.2 1069.41  5149.6 1070.61  5163.7 1070.48  5241.4 1074.39  5248.8  1076.3
  5262.9 1075.33  5342.3 1078.64  5411.4 1081.48  5439.8 1081.68  5510.4 1085.64
#Mann= 7 ,-1 , 0
  4197.3     .05       0  4941.2     .12       0  4992.5     .07       0
  5000.3     .12       0  5042.7     .05       0  5060.8     .12       0
  5342.3     .05       0
Bank Sta=4992.5,5000.3
XS Rating Curve= 0 ,0
Exp/Cntr=0.3,0.1

Type RM Length L Ch R = 1 ,26500   ,500,500,500
BEGIN DESCRIPTION:
CAMPGROUND CREEK 53.0
END DESCRIPTION:
XS GIS Cut Line= 3
      2881555.68     10272053.11      2881223.11     10271537.09
      2880705.68     10271053.11
#Sta/Elev= 30
  4386.1 1082.98  4393.7 1081.12    4430 1078.74  4523.7 1075.44  4647.8  1073.3
  4762.7 1067.34  4820.1  1066.8  4835.3  1064.7  4898.7 1063.02    4929 1061.19
    4931 1060.12  4931.5 1059.62  4938.9 1060.12  4950.2 1061.11  5008.2 1060.26
  5043.4 1062.87  5085.9 1063.47  5142.6 1063.64  5163.6 1062.55  5199.2 1065.12
  5255.9 1066.79  5361.9 1068.37  5425.4 1070.64  5453.7 1072.92  5461.1 1074.74
  5467.9 1073.85  5510.4 1074.83  5637.9  1081.5  5687.2 1082.29  5708.5 1084.16
#Mann= 3 ,-1 , 0
  4386.1     .05       0    4931     .03       0  4938.9     .05       0
Bank Sta=4931,4938.9
XS Rating Curve= 0 ,0
Exp/Cntr=0.3,0.1

Type RM Length L Ch R = 1 ,26000   ,500,500,500
BEGIN DESCRIPTION:
CAMPGROUND CREEK 52.0
END DESCRIPTION:
XS GIS Cut Line= 3
      2881605.67     10271403.08      2881524.17     10271161.57
      2881155.65     10270953.09
#Sta/Elev= 30
  4745.1 1070.94  4755.5 1071.34  4760.8 1068.76  4766.2 1069.39  4829.5 1063.93
  4855.2 1062.72  4881.4 1059.37  4886.7 1060.22  4903.4 1057.11  4924.5 1056.65
  4949.6 1054.36  4975.8 1054.12  4981.1 1052.82    5000 1052.89  5001.5 1050.22
    5002 1049.72  5009.5 1050.22  5021.2 1050.39  5032.9 1052.82  5055.7  1053.8
  5064.7 1056.08  5070.4 1055.11  5086.3 1061.59  5092.1  1059.7    5108 1063.07
  5136.1 1064.84  5188.8 1064.09  5210.5 1065.77  5226.4 1065.05  5423.4 1072.12
#Mann= 3 ,-1 , 0
  4745.1     .05       0  5001.5     .05       0  5009.5     .05       0
Bank Sta=5001.5,5009.5
XS Rating Curve= 0 ,0
Exp/Cntr=0.3,0.1

Type RM Length L Ch R = 1 ,25500   ,500,500,500
BEGIN DESCRIPTION:
CAMPGROUND CREEK 51.0
END DESCRIPTION:
XS GIS Cut Line= 3
      2881955.69     10271403.13      2881748.64     10270733.82
      2881555.68      10270253.1
#Sta/Elev= 30
  4299.4 1069.89  4341.3 1070.56  4362.2 1068.31    4381 1068.62  4418.8 1066.65
    4446 1068.12  4456.7 1066.51  4498.3 1066.41  4540.2 1065.04  4554.5 1065.49
  4690.3  1059.5  4948.4 1050.65  4969.3 1048.77  5003.1 1048.37  5015.1  1046.4
  5015.6  1045.9  5023.2  1046.4  5043.3 1050.59  5119.3 1055.02  5258.5    1061
  5263.9 1062.08  5288.1 1061.49  5293.5 1062.25  5312.3 1061.84  5317.7 1063.08
  5334.8 1062.43  5385.8 1063.04  5454.8 1064.88  5515.1 1070.86    5518 1070.88
#Mann= 5 ,-1 , 0
  4299.4     .05       0  5015.1     .03       0  5023.2     .05       0
  5385.8     .12       0  5515.1     .05       0
Bank Sta=5015.1,5023.2
XS Rating Curve= 0 ,0
Exp/Cntr=0.3,0.1

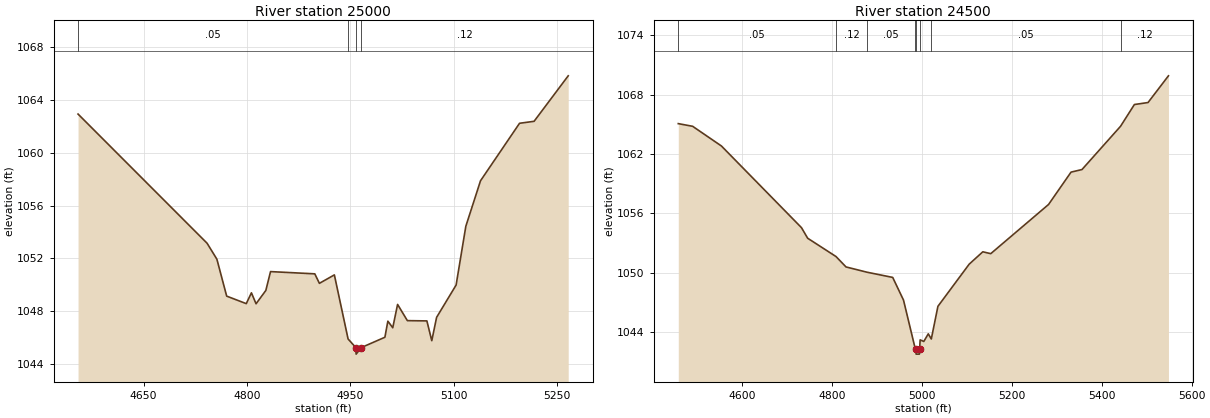
Type RM Length L Ch R = 1 ,25000   ,500,500,500
BEGIN DESCRIPTION:
CAMPGROUND CREEK 50.0
END DESCRIPTION:
XS GIS Cut Line= 3
      2882422.79     10270740.76      2882092.62     10270442.27
      2881905.71     10270253.14
#Sta/Elev= 30
  4554.9 1062.94  4742.1 1053.14  4756.3 1051.93  4770.5 1049.13  4798.9 1048.56
  4806.4 1049.38  4813.1 1048.55  4827.3 1049.56  4834.1 1050.99  4898.3 1050.82
    4905  1050.1  4926.7 1050.74  4946.6 1045.88  4957.8 1045.23  4958.3 1044.73
  4965.9 1045.23    5000 1046.01  5004.3 1047.23  5011.4 1046.73  5018.4  1048.5
  5032.6 1047.27  5060.9 1047.25    5068 1045.75    5075 1047.52  5103.3 1049.97
  5117.4 1054.43  5138.7 1057.88  5195.3 1062.24  5216.4 1062.39  5265.9 1065.84
#Mann= 4 ,-1 , 0
  4554.9     .05       0  4946.6     .12       0  4957.8     .07       0
  4965.9     .12       0
Bank Sta=4957.8,4965.9
XS Rating Curve= 0 ,0
Exp/Cntr=0.3,0.1

Type RM Length L Ch R = 1 ,24500   ,500,500,500
BEGIN DESCRIPTION:
CAMPGROUND CREEK 49.0
END DESCRIPTION:
XS GIS Cut Line= 3
      2882605.68     10270703.11      2882419.39     10270195.09
      2881905.69     10270003.11
#Sta/Elev= 30
  4458.9 1065.06  4490.8 1064.79  4554.8  1062.8  4732.7 1054.55  4746.5 1053.48
  4809.5 1051.63  4831.7 1050.58  4878.1 1050.05  4935.5 1049.52  4959.5 1047.23
  4984.4 1042.54    4987 1042.27  4987.5 1041.77  4994.8 1041.77  4995.3 1042.27
  4996.5 1043.21  5004.6 1043.05  5014.6 1043.82  5021.3  1043.3    5036  1046.6
  5105.5 1050.86  5135.8 1052.11  5153.4 1051.92  5281.9 1056.89  5331.9 1060.16
  5356.2 1060.42  5441.9 1064.79  5472.7 1066.99    5503 1067.19  5548.4 1069.89
#Mann= 8 ,-1 , 0
  4458.9     .05       0  4809.5     .12       0  4878.1     .05       0
  4984.4     .12       0    4987     .07       0  4995.3     .12       0
  5021.3     .05       0  5441.9     .12       0
Bank Sta=4987,4995.3
XS Rating Curve= 0 ,0
Exp/Cntr=0.3,0.1