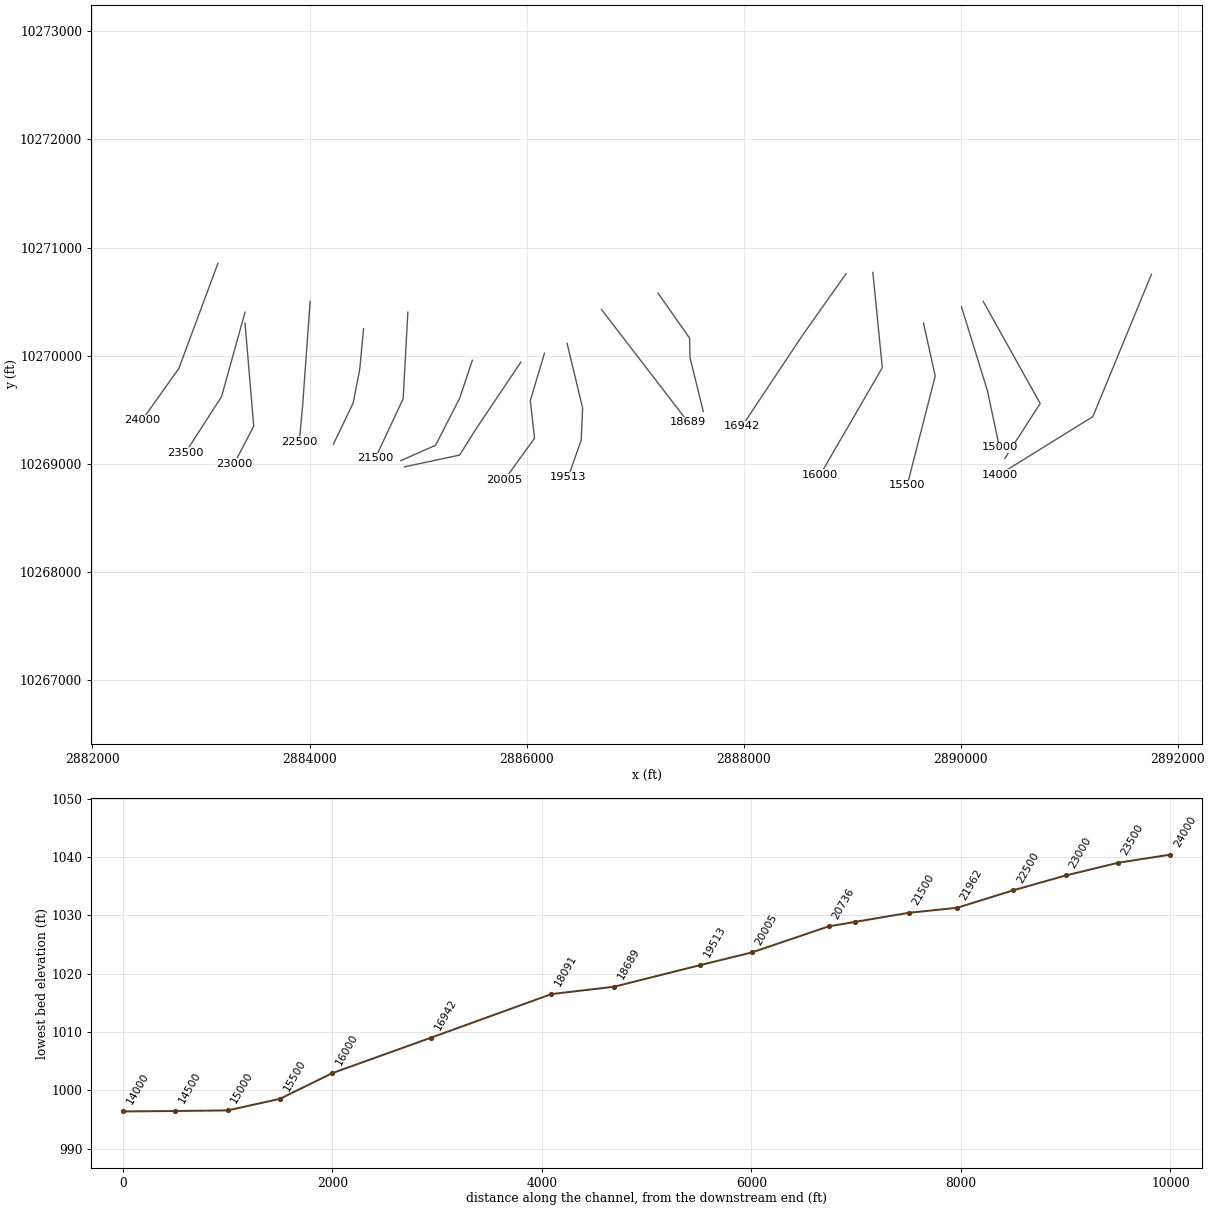
HEC-RAS study CAMPGROUND CREEK.prj: CAMPGROUND CREEK Base Level Engineering

--- CAMPGROUND CREEK.g01 (geometry) --- (continued)

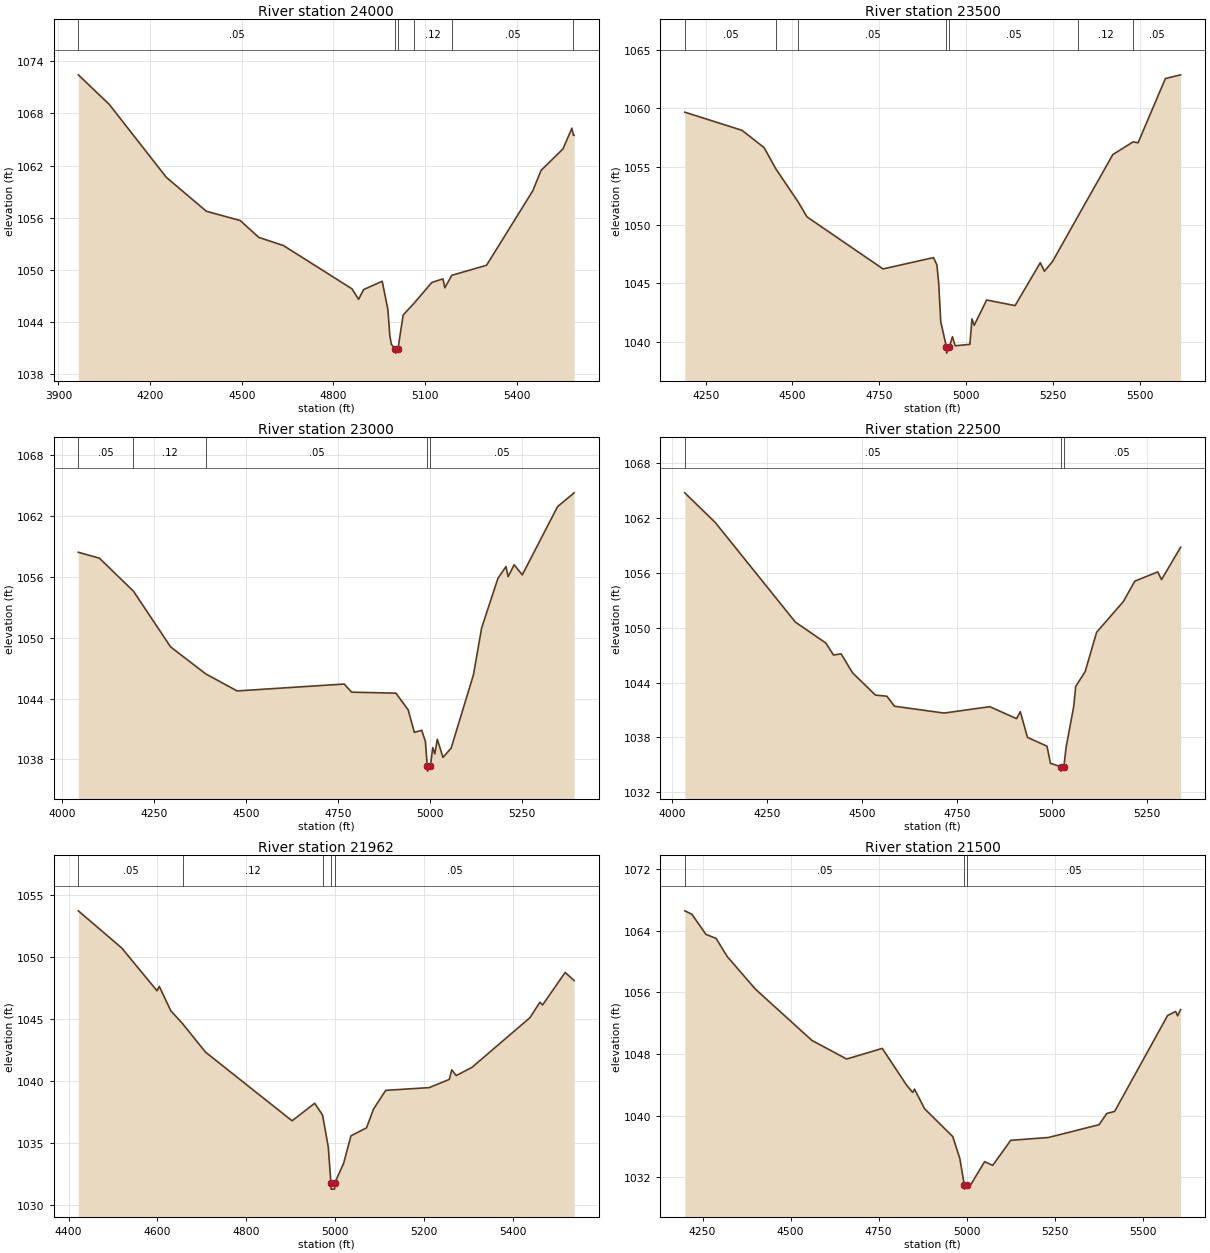
Type RM Length L Ch R = 1 ,24000   ,500,500,500
BEGIN DESCRIPTION:
CAMPGROUND CREEK 48.0
END DESCRIPTION:
XS GIS Cut Line= 3
      2883155.68     10270853.11      2882795.68     10269882.74
      2882455.69     10269403.12
#Sta/Elev= 30
    3965 1072.44    4066 1069.05    4253 1060.65  4384.1 1056.75  4494.9 1055.68
  4555.7 1053.74  4636.1 1052.81  4860.9 1047.82  4882.3 1046.62  4898.8 1047.74
  4959.6  1048.7  4978.3 1045.44  4984.6 1042.41  4989.9 1041.42    5003 1040.93
  5003.5 1040.43  5011.4 1040.93  5028.1 1044.81  5063.4 1046.15  5122.1 1048.56
  5158.5 1048.97  5164.6 1047.95  5187.5 1049.38  5301.2 1050.54  5452.6 1059.11
  5479.6 1061.45  5551.1 1063.91  5580.5  1066.3  5585.6 1065.48  5587.9 1065.48
#Mann= 6 ,-1 , 0
    3965     .05       0    5003     .05       0  5011.4     .05       0
  5063.4     .12       0  5187.5     .05       0  5585.6     .12       0
Bank Sta=5003,5011.4
XS Rating Curve= 0 ,0
Exp/Cntr=0.3,0.1

Type RM Length L Ch R = 1 ,23500   ,500,500,500
BEGIN DESCRIPTION:
CAMPGROUND CREEK 47.0
END DESCRIPTION:
XS GIS Cut Line= 3
      2883405.69     10270403.12      2883189.43     10269622.52
      2882855.68     10269103.11
#Sta/Elev= 30
    4190 1059.66  4354.7 1058.11  4418.3 1056.63  4452.3  1054.8    4517 1051.95
  4541.7  1050.7  4760.7 1046.24    4906 1047.21  4915.8 1046.58    4921 1044.99
  4926.8 1041.74  4943.3 1039.53  4943.8 1039.03  4951.7 1039.53  4960.5 1040.44
  4968.3 1039.66  5010.7 1039.78  5016.7 1041.96  5023.1 1041.41  5058.9 1043.58
  5140.8  1043.1  5213.3 1046.77  5225.4 1046.04  5248.9 1046.89    5323 1050.81
  5422.2 1056.03  5480.6 1057.12  5494.9 1057.04  5573.5 1062.54  5617.4 1062.86
#Mann= 7 ,-1 , 0
    4190     .05       0  4452.3     .12       0    4517     .05       0
  4943.3     .03       0  4951.7     .05       0    5323     .12       0
  5480.6     .05       0
Bank Sta=4943.3,4951.7
XS Rating Curve= 0 ,0
Exp/Cntr=0.3,0.1

Type RM Length L Ch R = 1 ,23000   ,500,500,500
BEGIN DESCRIPTION:
CAMPGROUND CREEK 46.0
END DESCRIPTION:
XS GIS Cut Line= 3
      2883405.68     10270303.13      2883485.88       10269350.
      2883305.68     10269003.11
#Sta/Elev= 30
  4043.5 1058.44  4100.9 1057.85  4193.3  1054.6  4294.4  1049.1  4389.8 1046.44
    4475 1044.76  4766.1 1045.44  4786.1 1044.64  4906.6 1044.54  4939.9 1042.89
  4956.7 1040.67  4976.8 1040.88  4986.8 1039.74  4991.7 1037.35  4992.2 1036.85
  5000.2 1037.35  5006.7 1039.17  5012.3 1038.55    5019 1039.99  5034.4 1038.21
  5056.6 1039.12  5117.3 1046.36  5139.4 1050.96  5183.6 1055.85  5205.7 1057.03
  5211.4 1056.03  5227.8  1057.2    5250 1056.21  5345.8 1062.94  5390.9  1064.3
#Mann= 5 ,-1 , 0
  4043.5     .05       0  4193.3     .12       0  4389.8     .05       0
  4991.7     .05       0  5000.2     .05       0
Bank Sta=4991.7,5000.2
XS Rating Curve= 0 ,0
Exp/Cntr=0.3,0.1

Type RM Length L Ch R = 1 ,22500   ,538,538,538
BEGIN DESCRIPTION:
CAMPGROUND CREEK 45.0
END DESCRIPTION:
XS GIS Cut Line= 3
      2884005.69     10270503.14       2883936.3     10269539.63
      2883905.69     10269203.12
#Sta/Elev= 30
    4034 1064.75  4114.2  1061.5  4324.8 1050.61    4405 1048.32    4425 1047.01
  4445.1 1047.14  4475.2 1045.06  4535.3 1042.63  4565.4  1042.5  4585.4 1041.41
  4715.8 1040.66  4836.1 1041.36  4906.3 1040.05  4916.3 1040.81  4935.2    1038
  4986.5 1037.04  4995.7 1035.16  5022.3 1034.81  5022.8 1034.31  5030.9 1034.81
  5036.7 1036.91  5056.8 1041.39  5061.9 1043.57  5086.9  1045.2    5117  1049.5
  5187.3 1052.86  5217.4 1055.09  5277.7  1056.1  5287.7 1055.26  5337.9  1058.8
#Mann= 3 ,-1 , 0
    4034     .05       0  5022.3     .05       0  5030.9     .05       0
Bank Sta=5022.3,5030.9
XS Rating Curve= 0 ,0
Exp/Cntr=0.3,0.1

Type RM Length L Ch R = 1 ,21962   ,462,462,462
BEGIN DESCRIPTION:
Mapping XS f9f824b2
END DESCRIPTION:
XS GIS Cut Line= 4
      2884497.47     10270250.32      2884462.75     10269877.07
      2884401.99     10269564.57      2884220.18     10269183.64
#Sta/Elev= 30
    4422  1053.7  4519.6 1050.71  4599.1 1047.26  4604.1 1047.62  4630.1 1045.65
  4656.5 1044.62  4708.3 1042.32  4902.8  1036.8  4953.7 1038.21  4971.4 1037.26
  4984.3 1034.68  4990.1  1031.8  4990.6  1031.3  4998.3  1031.3  4998.8  1031.8
  5018.6 1033.36  5035.2 1035.59  5070.2 1036.23  5086.1 1037.75  5113.4 1039.25
  5211.1 1039.47  5256.4 1040.13    5262  1040.9    5272 1040.44  5307.4  1041.1
  5437.9  1045.1  5460.3 1046.35  5466.2 1046.12  5517.1 1048.74  5537.3 1048.09
#Mann= 5 ,-1 , 0
    4422     .05       0  4656.5     .12       0  4971.4     .05       0
  4990.1     .05       0  4998.8     .05       0
Bank Sta=4990.1,4998.8
XS Rating Curve= 0 ,0
Exp/Cntr=0.3,0.1

Type RM Length L Ch R = 1 ,21500   ,516,516,516
BEGIN DESCRIPTION:
CAMPGROUND CREEK 43.0
END DESCRIPTION:
XS GIS Cut Line= 3
      2884905.69     10270403.14       2884862.5     10269603.81
       2884605.7     10269053.14
#Sta/Elev= 30
  4199.5 1066.59  4219.6 1066.15  4259.6 1063.53  4288.4 1063.01  4319.7 1060.67
  4399.8 1056.43  4560.1 1049.77  4659.1 1047.34  4760.3 1048.72  4830.5 1043.87
  4846.9    1043  4851.9 1043.43  4880.5 1040.88  4960.6 1037.26  4980.7 1034.39
  4993.4 1030.94  4993.9 1030.44  5002.2 1030.94  5011.8 1031.04    5051 1034.01
  5073.9 1033.52  5125.1 1036.78  5232.5 1037.15  5375.9 1038.81    5398 1040.27
  5420.1 1040.53  5570.6 1052.99  5593.4 1053.52    5599 1052.95  5607.6 1053.77
#Mann= 3 ,-1 , 0
  4199.5     .05       0  4993.4     .03       0  5002.2     .05       0
Bank Sta=4993.4,5002.2
XS Rating Curve= 0 ,0
Exp/Cntr=0.3,0.1

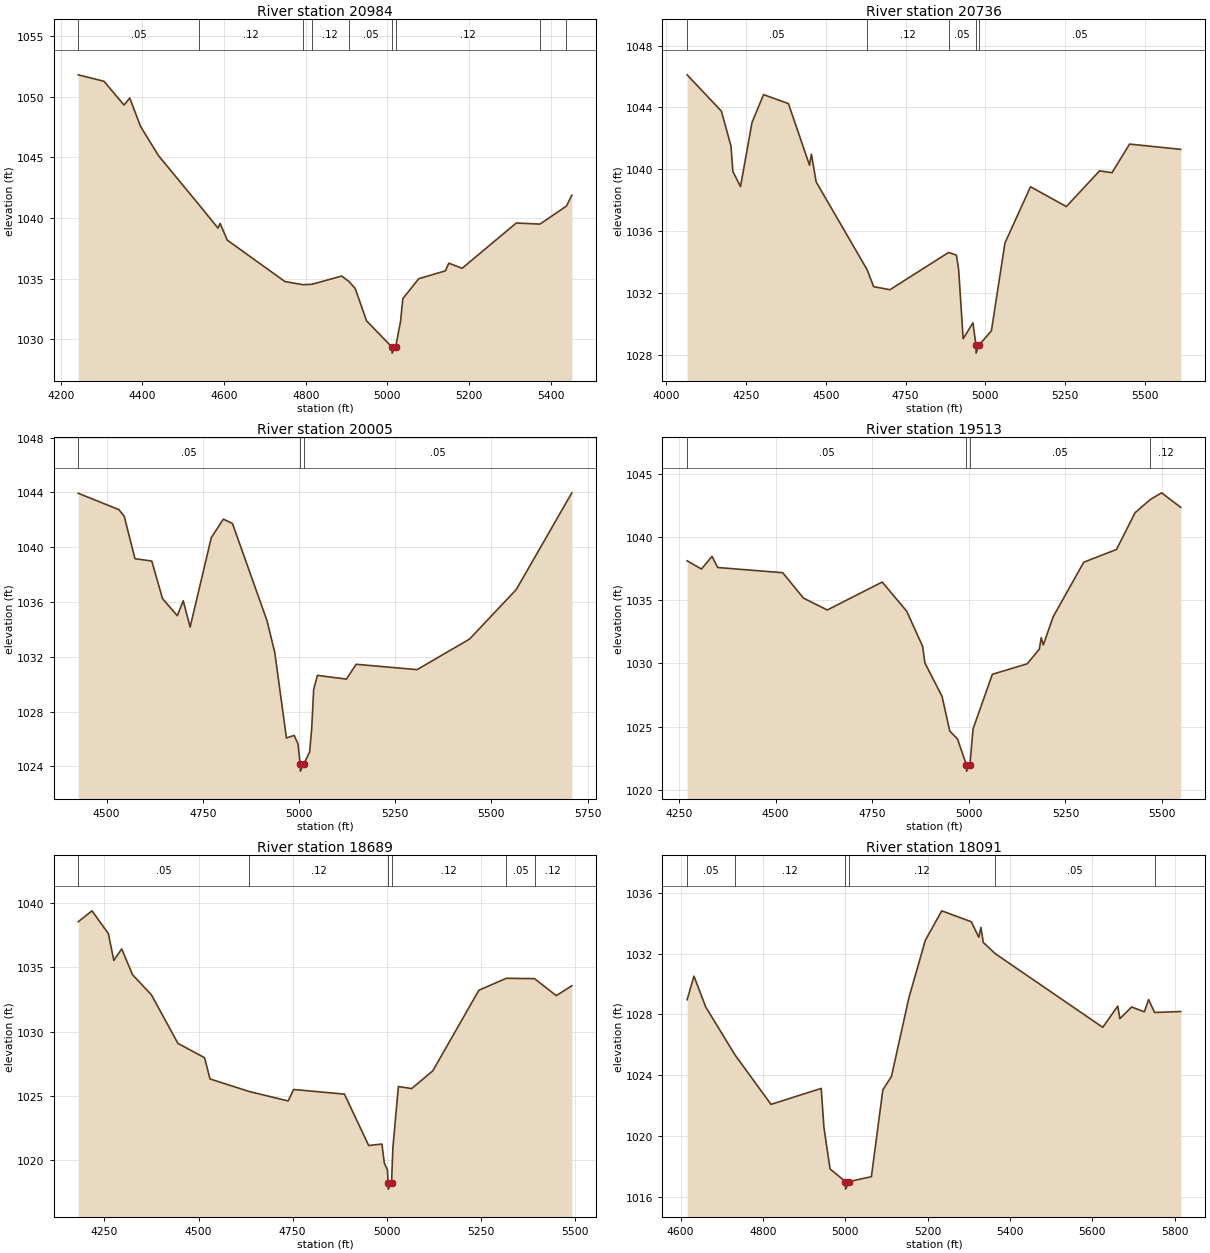
Type RM Length L Ch R = 1 ,20984   ,248,248,248
BEGIN DESCRIPTION:
Mapping XS dea59232
END DESCRIPTION:
XS GIS Cut Line= 4
      2885500.09     10269959.56      2885382.89     10269607.98
      2885161.54     10269173.95      2884840.53      10269030.8
#Sta/Elev= 30
  4242.7  1051.8  4305.8 1051.27  4354.9 1049.31    4369 1049.89  4395.4 1047.55
  4439.2 1045.15  4537.5 1041.14  4585.1 1039.17  4590.4 1039.55  4607.9 1038.18
    4749 1034.77  4792.7 1034.51  4815.2 1034.54  4888.2 1035.22  4905.4 1034.79
  4921.3  1034.2  4949.1 1031.53  5011.3 1029.37  5011.8 1028.87  5020.3 1029.37
  5032.4 1031.48    5038 1033.36  5076.9    1035  5142.3 1035.65  5150.7 1036.28
  5183.3 1035.86  5315.9 1039.59    5374  1039.5  5438.9 1040.99    5452 1041.88
#Mann= 9 ,-1 , 0
  4242.7     .05       0  4537.5     .12       0  4792.7     .05       0
  4815.2     .12       0  4905.4     .05       0  5011.3     .03       0
  5020.3     .12       0    5374     .12       0  5438.9     .05       0
Bank Sta=5011.3,5020.3
XS Rating Curve= 0 ,0
Exp/Cntr=0.3,0.1

Type RM Length L Ch R = 1 ,20736   ,731,731,731
BEGIN DESCRIPTION:
Mapping XS 71a963f6
END DESCRIPTION:
XS GIS Cut Line= 4
      2885947.14      10269942.2      2885526.12     10269312.84
      2885382.89      10269082.8      2884875.04     10268974.29
#Sta/Elev= 30
  4064.9 1046.11  4172.3 1043.76  4202.3 1041.51  4208.3 1039.86  4232.2 1038.88
  4268.3 1043.03  4304.4 1044.83  4382.4 1044.25  4448.5 1040.27  4454.5 1040.98
  4469.5 1039.18  4629.1 1033.51  4649.7 1032.41  4700.7 1032.21  4884.5 1034.62
  4909.1 1034.45    4916 1033.54  4930.3 1029.04    4961 1030.07  4970.4 1028.61
  4970.9 1028.11  4979.4 1028.61  5018.9 1029.56  5061.3 1035.23  5141.4 1038.87
  5253.8 1037.59    5358  1039.9    5397 1039.78  5451.9 1041.63  5612.4 1041.29
#Mann= 5 ,-1 , 0
  4064.9     .05       0  4629.1     .12       0  4884.5     .05       0
  4970.4     .03       0  4979.4     .05       0
Bank Sta=4970.4,4979.4
XS Rating Curve= 0 ,0
Exp/Cntr=0.3,0.1

Type RM Length L Ch R = 1 ,20005   ,492,492,492
BEGIN DESCRIPTION:
Mapping XS 7c4c83fe
END DESCRIPTION:
XS GIS Cut Line= 4
      2886164.13     10270024.61      2886033.93     10269586.27
      2886072.99     10269239.05       2885795.2     10268852.74
#Sta/Elev= 30
  4426.4 1043.94  4532.3 1042.74  4545.9 1042.26  4573.9 1039.16  4617.5 1038.99
  4645.5 1036.24  4683.9    1035  4699.2 1036.09  4717.2 1034.17  4772.2  1040.7
  4803.5 1042.05  4827.2 1041.73    4917 1034.63  4937.2  1032.3  4967.4 1026.07
  4987.5 1026.26  4997.5 1025.64  5003.1 1024.15  5003.6 1023.65  5012.2 1024.15
  5027.7 1025.05  5033.1 1026.78  5038.2 1029.62  5047.9 1030.64  5123.2 1030.37
  5148.5 1031.45  5306.8 1031.06  5443.1 1033.29  5564.6 1036.91  5708.9 1043.97
#Mann= 3 ,-1 , 0
  4426.4     .05       0  5003.1     .03       0  5012.2     .05       0
Bank Sta=5003.1,5012.2
XS Rating Curve= 0 ,0
Exp/Cntr=0.3,0.1

Type RM Length L Ch R = 1 ,19513   ,824,824,824
BEGIN DESCRIPTION:
Mapping XS 4f781bdc
END DESCRIPTION:
XS GIS Cut Line= 4
      2886372.48     10270115.77       2886515.7     10269516.83
      2886502.68     10269221.69      2886381.79     10268876.29
#Sta/Elev= 30
    4271 1038.12    4308 1037.47  4335.4 1038.47  4350.1 1037.59  4518.3 1037.18
  4571.9 1035.17  4633.6 1034.23  4775.8 1036.44  4839.2 1034.13  4880.4 1031.35
  4886.2 1030.04  4930.6 1027.39  4950.6 1024.65  4970.6 1024.02  4993.6 1021.98
  4994.1 1021.48  5002.8 1021.98  5010.7 1024.81  5060.7 1029.14  5150.8 1029.97
  5182.3 1031.13  5187.2 1032.04  5192.5 1031.46  5218.2  1033.7  5297.3 1038.01
    5382 1039.02  5430.1 1041.93  5469.8 1042.98  5498.6  1043.5  5548.2 1042.35
#Mann= 4 ,-1 , 0
    4271     .05       0  4993.6     .03       0  5002.8     .05       0
  5469.8     .12       0
Bank Sta=4993.6,5002.8
XS Rating Curve= 0 ,0
Exp/Cntr=0.3,0.1

Type RM Length L Ch R = 1 ,18689   ,598,598,598
BEGIN DESCRIPTION:
Mapping XS 1bb764a8
END DESCRIPTION:
XS GIS Cut Line= 2
      2886689.31     10270428.29      2887487.33     10269387.39
#Sta/Elev= 30
  4180.2 1038.53  4216.8 1039.38  4260.3 1037.61  4274.8 1035.53  4295.7 1036.42
  4324.7 1034.41  4374.6 1032.86  4445.2 1029.08  4515.9 1027.97  4530.4 1026.32
    4635 1025.34  4738.1 1024.61  4752.6  1025.5  4887.6 1025.14    4952 1021.15
  4987.3 1021.26  4993.6 1019.78  5001.9 1019.26  5003.5 1018.26    5004 1017.76
  5012.8 1018.26  5016.4    1021  5030.9 1025.73  5066.2 1025.57  5122.4 1026.95
  5244.8 1033.21  5317.8 1034.14  5392.9 1034.11  5450.5 1032.79  5491.8 1033.56
#Mann= 6 ,-1 , 0
  4180.2     .05       0    4635     .12       0  5003.5     .07       0
  5012.8     .12       0  5317.8     .05       0  5392.9     .12       0
Bank Sta=5003.5,5012.8
XS Rating Curve= 0 ,0
Exp/Cntr=0.3,0.1

Type RM Length L Ch R = 1 ,18091   ,1149,1149,1149
BEGIN DESCRIPTION:
Mapping XS 75b9a61a
END DESCRIPTION:
XS GIS Cut Line= 4
      2887210.16     10270580.18      2887500.94     10270163.53
      2887505.29     10269981.24      2887626.61     10269487.25
#Sta/Elev= 30
  4615.8 1028.97  4632.4 1030.52    4661 1028.49  4732.2 1025.33  4819.5 1022.08
  4941.5 1023.13  4948.1 1020.56    4963 1017.83  5000.2    1017  5000.7  1016.5
  5009.5    1017  5063.4 1017.32  5091.2 1023.03  5112.2 1023.92  5154.3 1029.07
  5194.3 1032.87  5234.3 1034.82  5306.2  1034.1  5324.3 1033.08  5329.5 1033.73
  5335.2 1032.74  5364.3    1032  5625.5 1027.15  5661.9 1028.55  5667.1 1027.72
  5695.6 1028.49  5726.5 1028.17  5736.8 1028.98  5751.3 1028.13  5814.9 1028.19
#Mann= 6 ,-1 , 0
  4615.8     .05       0  4732.2     .12       0  5000.2     .07       0
  5009.5     .12       0  5364.3     .05       0  5751.3     .12       0
Bank Sta=5000.2,5009.5
XS Rating Curve= 0 ,0
Exp/Cntr=0.3,0.1

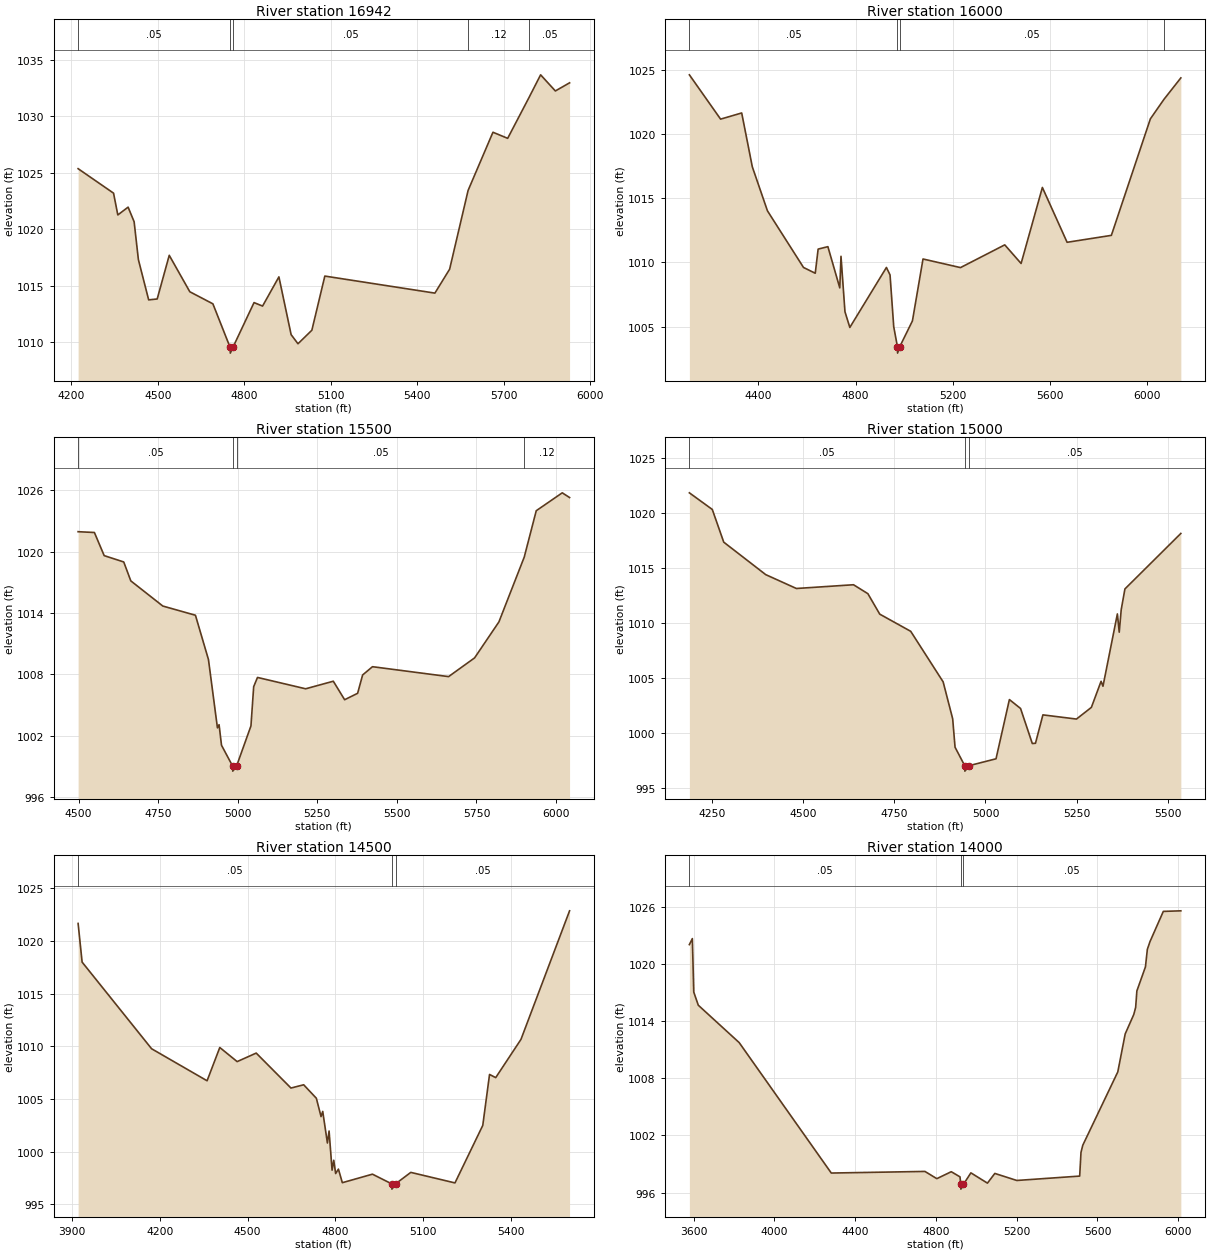
Type RM Length L Ch R = 1 ,16942   ,942,942,942
BEGIN DESCRIPTION:
Mapping XS 37ade52a
END DESCRIPTION:
XS GIS Cut Line= 3
      2888941.91     10270758.14      2888546.95     10270198.25
      2887982.87      10269347.8
#Sta/Elev= 30
  4223.4 1025.37  4346.4  1023.2  4361.2 1021.27  4396.9 1021.96  4417.8 1020.67
  4432.6 1017.31  4468.3 1013.74  4497.9 1013.82  4539.7 1017.69  4611.1 1014.46
  4691.2 1013.39  4751.1 1009.52  4751.6 1009.02  4760.5 1009.52    4834  1013.5
  4863.6 1013.19  4920.3 1015.78  4962.7 1010.66  4986.5 1009.85  5034.7 1011.05
  5079.7 1015.85  5461.7 1014.34  5512.8 1016.46  5576.9 1023.44  5663.2  1028.6
  5714.3 1028.06  5788.6 1031.69  5828.6 1033.69  5879.8 1032.26  5929.1 1032.98
#Mann= 5 ,-1 , 0
  4223.4     .05       0  4751.1     .03       0  4760.5     .05       0
  5576.9     .12       0  5788.6     .05       0
Bank Sta=4751.1,4760.5
XS Rating Curve= 0 ,0
Exp/Cntr=0.3,0.1

Type RM Length L Ch R = 1 ,16000   ,500,500,500
BEGIN DESCRIPTION:
CAMPGROUND CREEK 32.0
END DESCRIPTION:
XS GIS Cut Line= 3
      2889189.32     10270771.12      2889276.38     10269890.72
      2888705.71     10268903.15
#Sta/Elev= 30
  4115.3 1024.61  4243.9 1021.16  4330.9 1021.64  4374.6 1017.45    4437 1014.02
  4585.6 1009.61    4634 1009.16  4645.9 1011.04  4686.1 1011.23  4735.1 1008.02
  4740.1 1010.48  4756.4 1006.17  4776.5 1004.94  4927.3 1009.61  4942.2 1009.03
  4957.4    1005  4972.7 1003.44  4973.2 1002.94  4982.2 1003.44  5034.5 1005.45
  5078.1 1010.27  5232.6  1009.6    5415 1011.37  5482.3 1009.92    5570 1015.84
  5671.9 1011.57  5854.3 1012.11    6015 1021.18  6071.4 1022.71  6140.6 1024.37
#Mann= 4 ,-1 , 0
  4115.3     .05       0  4972.7     .03       0  4982.2     .05       0
  6071.4     .12       0
Bank Sta=4972.7,4982.2
XS Rating Curve= 0 ,0
Exp/Cntr=0.3,0.1

Type RM Length L Ch R = 1 ,15500   ,500,500,500
BEGIN DESCRIPTION:
CAMPGROUND CREEK 31.0
END DESCRIPTION:
XS GIS Cut Line= 3
      2889655.69     10270303.09      2889763.93     10269813.21
      2889505.68      10268803.1
#Sta/Elev= 30
  4498.3 1021.94  4549.5 1021.86  4580.2  1019.6  4641.7 1018.98  4663.9 1017.13
  4764.5 1014.67    4867 1013.77  4907.9 1009.44  4936.1 1002.76  4941.2 1003.07
  4948.9 1001.06  4983.7  999.03  4984.2  998.53  4996.3  999.03  5041.4 1002.95
    5050 1006.79    5062 1007.69  5213.3 1006.58  5300.2 1007.32  5335.8 1005.51
  5376.6 1006.14  5392.3 1007.93  5423.3 1008.74  5662.4 1007.77  5744.1  1009.6
  5820.6 1013.12  5900.1 1019.45  5937.9 1023.99  6019.6 1025.74  6042.6 1025.28
#Mann= 4 ,-1 , 0
  4498.3     .05       0  4983.7     .03       0  4996.3     .05       0
  5900.1     .12       0
Bank Sta=4983.7,4996.3
XS Rating Curve= 0 ,0
Exp/Cntr=0.3,0.1

Type RM Length L Ch R = 1 ,15000   ,500,500,500
BEGIN DESCRIPTION:
CAMPGROUND CREEK 30.0
END DESCRIPTION:
XS GIS Cut Line= 3
      2890005.69     10270453.11      2890244.87     10269677.35
      2890355.68     10269153.13
#Sta/Elev= 30
  4188.2 1021.82    4251 1020.31  4282.4 1017.34  4397.5 1014.39  4481.6 1013.13
  4638.2 1013.47  4677.6 1012.66  4710.2  1010.8  4795.1 1009.24    4884 1004.65
  4910.2 1001.29  4916.7  998.71  4943.1  997.04  4943.6  996.54  4955.7  997.04
    5029  997.66  5065.7 1003.04  5096.3 1002.23  5128.5  999.05  5137.2  999.07
  5157.6 1001.65  5249.6 1001.27  5290.5 1002.33  5317.1  1004.7  5322.3 1004.25
  5361.8 1010.82  5366.9 1009.16  5372.3 1011.21  5382.5 1013.09  5535.8 1018.13
#Mann= 3 ,-1 , 0
  4188.2     .05       0  4943.1     .03       0  4955.7     .05       0
Bank Sta=4943.1,4955.7
XS Rating Curve= 0 ,0
Exp/Cntr=0.3,0.1

Type RM Length L Ch R = 1 ,14500   ,500,500,500
BEGIN DESCRIPTION:
CAMPGROUND CREEK 29.0
END DESCRIPTION:
XS GIS Cut Line= 3
       2890205.7     10270503.09       2890730.8     10269559.57
       2890405.7     10269053.14
#Sta/Elev= 30
  3920.2 1021.67  3933.9    1018  4171.7 1009.77  4361.5 1006.73    4405 1009.89
  4464.4 1008.55  4529.6 1009.36  4648.5 1006.04    4692 1006.35  4735.4 1005.07
  4751.4 1003.33  4757.2 1003.82  4773.2 1000.82  4778.9 1001.96  4789.2  998.24
  4794.9  999.18  4801.4  997.92  4810.9  998.34  4824.3  997.05  4927.3  997.86
  4993.4  996.94  4993.9  996.44  5006.4  996.94  5058.5  998.03  5209.7  997.03
  5304.8 1002.49    5328 1007.33  5349.1 1007.03  5435.5 1010.66  5601.8 1022.87
#Mann= 3 ,-1 , 0
  3920.2     .05       0  4993.4     .03       0  5006.4     .05       0
Bank Sta=4993.4,5006.4
XS Rating Curve= 0 ,0
Exp/Cntr=0.3,0.1

Type RM Length L Ch R = 1 ,14000   ,0,0,0
BEGIN DESCRIPTION:
CAMPGROUND CREEK 28.0
END DESCRIPTION:
XS GIS Cut Line= 3
       2891755.7     10270753.15      2891215.76     10269438.08
      2890355.67      10268903.1
#Sta/Elev= 30
  3578.4 1022.06  3593.1 1022.69  3600.1 1017.07  3622.5 1015.69  3825.1 1011.76
  4281.3  998.05  4745.3  998.22  4804.1  997.46  4875.7  998.19  4918.9  997.65
  4922.7  996.86  4923.2  996.36  4935.9  996.86  4972.9  998.07  5054.9  996.99
  5091.5  998.01  5200.3  997.27  5511.8  997.73  5518.3 1000.22  5527.1 1000.97
  5700.6 1008.68  5737.2 1012.67  5779.7 1014.71  5789.1 1015.46  5795.1 1017.19
  5837.6 1019.72    5847 1021.56  5859.8 1022.36  5926.1 1025.55  6012.9 1025.61
#Mann= 3 ,-1 , 0
  3578.4     .05       0  4922.7     .03       0  4935.9     .05       0
Bank Sta=4922.7,4935.9
XS Rating Curve= 0 ,0
Exp/Cntr=0.3,0.1

Chan Stop Cuts=-1
Use User Specified Reach Order=0