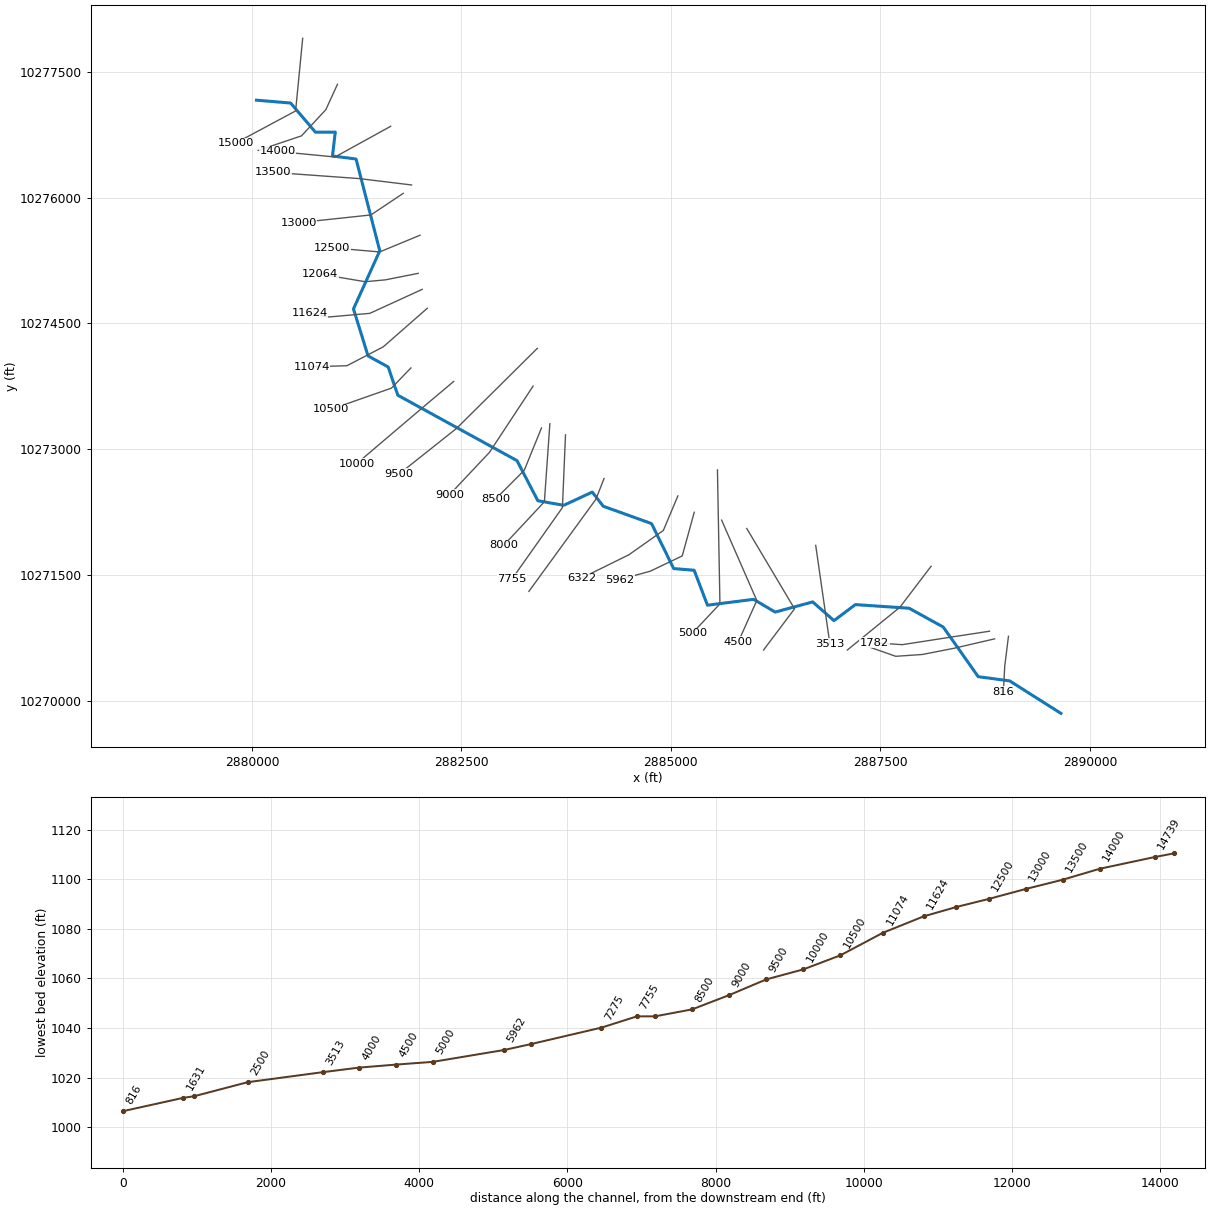
--- COLORADO 01.prj (project) ---

Proj Title=COLORADO 01 Base Level Engineering
Current Plan=p01
Default Exp/Contr=0.3,0.1
English Units
Geom File=g01
Flow File=f01
Plan File=p01
Y Axis Title=Elevation
X Axis Title(PF)=Main Channel Distance
X Axis Title(XS)=Station
BEGIN DESCRIPTION:
COLORADO 01
END DESCRIPTION:
DSS Export Rating Curves= 0
DSS Export Rating Curve Sorted= 0
DSS Export Volume Flow Curves= 0
DXF OffsetX= 0
DXF OffsetY= 0
DXF ScaleX= 1
DXF ScaleY= 10

--- COLORADO 01.p01 (plan) ---

Plan Title=Multiple Run
Short Identifier=Multiple
Geom File=g01
Flow File=f01
Subcritical Flow
K Sum by GR= 0
Std Step Tol= 0.01
Critical Tol= 0.01
Num of Std Step Trials= 20
Max Error Tol= 0.3
Flow Tol Ratio= 0.001
Split Flow NTrial= 30
Split Flow Tol= 0.02
Split Flow Ratio= 0.02
Log Output Level= 0
Friction Slope Method= 1
Unsteady Friction Slope Method= 2
Unsteady Bridges Friction Slope Method= 1
Parabolic Critical Depth
Global Vel Dist=  1 , 1 , 1
Global Log Level= 0
CheckData=True
Encroach Param= -1, 0, 0, 0
BEGIN DESCRIPTION:
Multiple Run
END DESCRIPTION:

--- COLORADO 01.f01 (steady flow) ---

Flow Title=Multiple
Number of Profiles=7
Profile Names=10-year,25-year,50-year,1pct_min,100-year,1pct_plu,500-year
River Rch & RM= COLORADO 01,Reach-1,15000
     518     854     939     564    1092    2113    1456
River Rch & RM= COLORADO 01,Reach-1,2500
     684    1148    1263     750    1487    2948    1974
Boundary for River Rch & Prof#=COLORADO 01,Reach-1,1
Up Type=0
Dn Type=3
Dn Slope=0.005
Boundary for River Rch & Prof#=COLORADO 01,Reach-1,2
Up Type=0
Dn Type=3
Dn Slope=0.005
Boundary for River Rch & Prof#=COLORADO 01,Reach-1,3
Up Type=0
Dn Type=3
Dn Slope=0.005
Boundary for River Rch & Prof#=COLORADO 01,Reach-1,4
Up Type=0
Dn Type=3
Dn Slope=0.005
Boundary for River Rch & Prof#=COLORADO 01,Reach-1,5
Up Type=0
Dn Type=3
Dn Slope=0.005
Boundary for River Rch & Prof#=COLORADO 01,Reach-1,6
Up Type=0
Dn Type=3
Dn Slope=0.005
Boundary for River Rch & Prof#=COLORADO 01,Reach-1,7
Up Type=0
Dn Type=3
Dn Slope=0.005

--- COLORADO 01.g01 (geometry) ---

Geom Title=Existing Conditions
Program Version=4.00

River Reach=COLORADO 01     ,Reach-1
Reach XY= 30
       2880054.5       10277165.        2880462.       10277131.
        2880758.       10276783.       2880994.5       10276784.
       2880961.5       10276499.      2881242.75       10276463.
      2881525.75       10275367.        2881212.       10274674.
      2881385.75       10274113.        2881626.       10273981.
        2881741.       10273644.      2883163.75       10272863.
        2883412.       10272385.        2883721.       10272330.
      2884061.75       10272488.        2884193.       10272319.
        2884769.       10272112.       2885033.5       10271575.
       2885277.5       10271555.      2885436.75       10271138.
        2885987.       10271208.       2886244.5       10271056.
       2886692.5       10271177.       2886946.5       10270954.
      2887200.75       10271145.       2887842.5       10271102.
      2888250.75       10270877.       2888667.5       10270285.
       2889042.5       10270235.        2889655.       10269847.

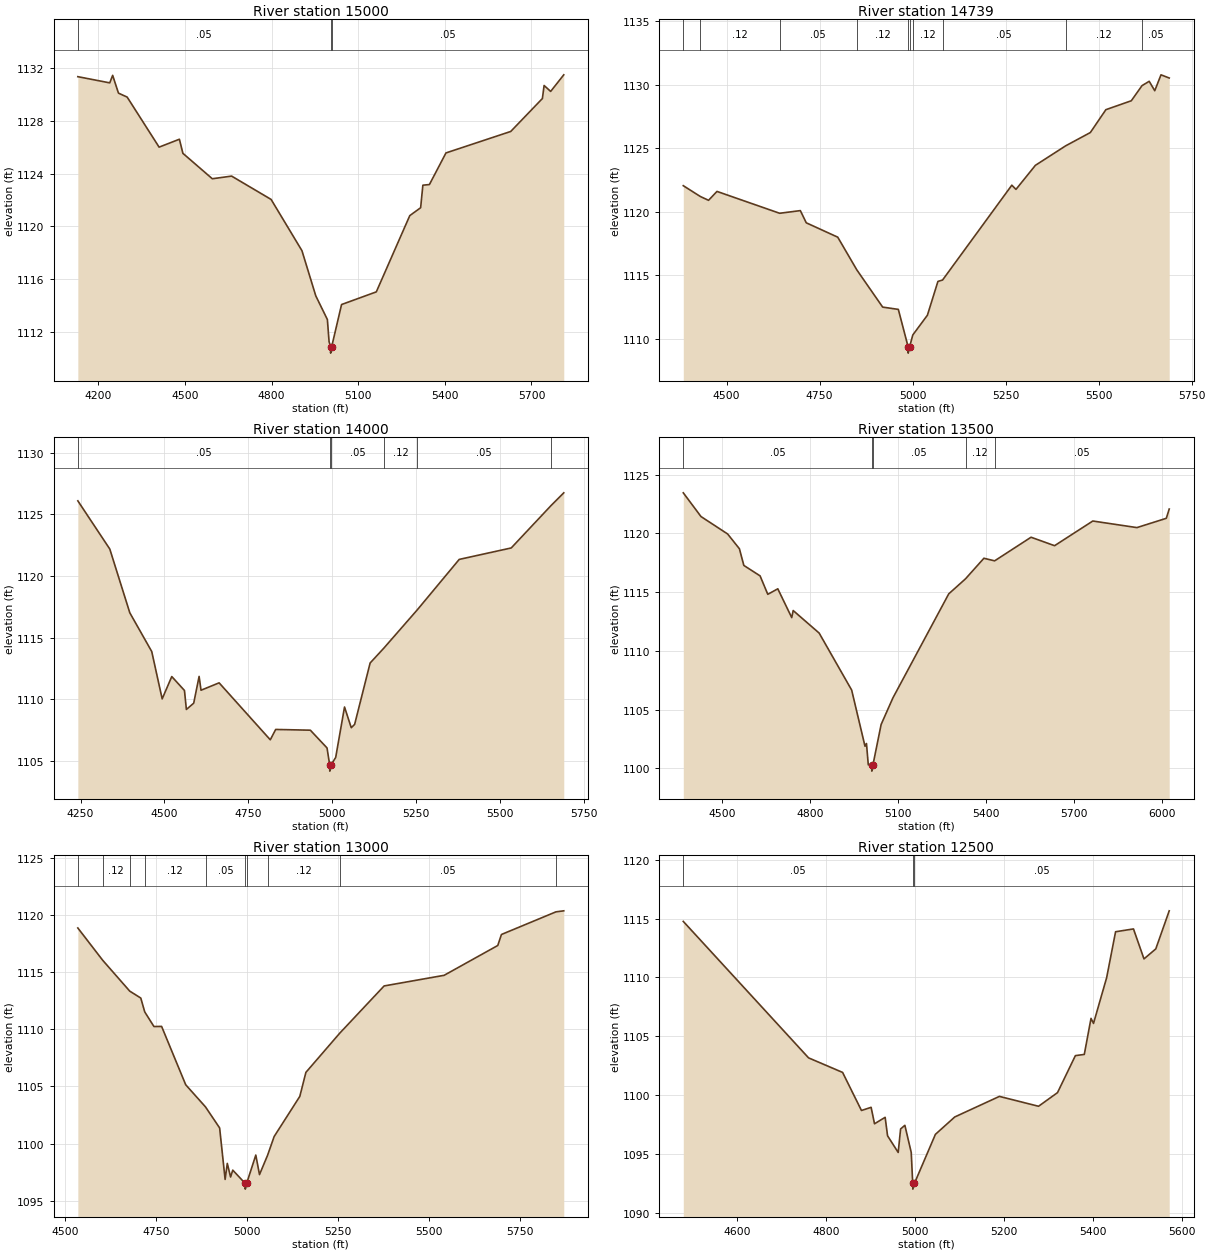
Type RM Length L Ch R = 1 ,15000   ,261,261,261
BEGIN DESCRIPTION:
COLORADO 01 30.0
END DESCRIPTION:
XS GIS Cut Line= 3
      2880605.69     10277903.14      2880521.23     10277036.44
      2879805.65     10276653.09
#Sta/Elev= 30
  4129.2 1131.36  4239.7 1130.89  4249.8 1131.46  4269.9 1130.11    4300 1129.81
  4410.6 1126.01  4480.9 1126.61    4493 1125.54  4594.8 1123.61  4661.7 1123.81
  4798.4 1122.04  4905.2 1118.15  4953.1 1114.72  4993.3 1112.92  4999.2 1111.23
  5004.3 1110.87  5004.5 1110.37  5008.3 1110.87  5042.4 1114.06  5162.7 1115.02
  5278.6 1120.81  5316.2 1121.41  5323.9 1123.12  5346.6 1123.17  5403.9 1125.57
  5628.2  1127.2  5737.8  1129.7  5743.7 1130.69  5766.4 1130.24  5811.8  1131.5
#Mann= 3 ,-1 , 0
  4129.2     .05       0  5004.3     .03       0  5008.3     .05       0
Bank Sta=5004.3,5008.3
XS Rating Curve= 0 ,0
Exp/Cntr=0.3,0.1

Type RM Length L Ch R = 1 ,14739   ,739,739,739
BEGIN DESCRIPTION:
Mapping XS 3dfed9e2
END DESCRIPTION:
XS GIS Cut Line= 4
      2881020.93     10277355.42      2880882.02     10277051.55
      2880591.22     10276739.05       2880074.7     10276565.43
#Sta/Elev= 30
  4383.8 1122.06  4429.6 1121.21  4451.7 1120.91  4474.3 1121.61  4642.8 1119.89
  4698.4  1120.1  4714.3 1119.14  4798.9 1118.01  4850.1 1115.44  4919.6 1112.51
  4961.7 1112.33    4988 1109.39  4988.2 1108.89    4992 1109.39  5000.6 1110.32
  5039.8 1111.87  5068.1 1114.53  5080.6 1114.64  5266.7  1122.1  5277.9 1121.77
    5330 1123.66  5411.1 1125.19  5477.7 1126.24  5519.5 1128.04  5587.8 1128.74
  5616.6 1129.93  5635.9 1130.27  5650.8 1129.53  5667.6 1130.78  5689.7 1130.53
#Mann= 10 ,-1 , 0
  4383.8     .05       0  4429.6     .12       0  4642.8     .05       0
  4850.1     .12       0    4988     .03       0    4992     .12       0
  5000.6     .12       0  5080.6     .05       0  5411.1     .12       0
  5616.6     .05       0
Bank Sta=4988,4992
XS Rating Curve= 0 ,0
Exp/Cntr=0.3,0.1

Type RM Length L Ch R = 1 ,14000   ,500,500,500
BEGIN DESCRIPTION:
COLORADO 01 28.0
END DESCRIPTION:
XS GIS Cut Line= 3
       2881655.7     10276853.12      2880991.72     10276487.27
      2880305.68     10276553.11
#Sta/Elev= 30
  4241.9  1126.1  4337.1 1122.19  4396.7 1117.02    4462 1113.88  4493.1 1110.04
  4521.7 1111.85  4559.5 1110.72  4565.2 1109.18    4587 1109.69  4603.1 1111.86
  4608.8 1110.74  4662.7 1111.34  4815.1 1106.72  4831.2 1107.56  4934.4  1107.5
  4984.1 1106.06    4992 1104.68  4992.3 1104.18    4996 1104.68  5009.9 1105.29
  5036.2 1109.38  5056.3  1107.7  5066.3 1107.97  5112.5 1112.95  5153.2 1114.15
  5252.9 1117.26  5377.8 1121.35  5532.8 1122.28  5651.4 1125.72  5689.2 1126.75
#Mann= 6 ,-1 , 0
  4241.9     .05       0    4992     .03       0    4996     .05       0
  5153.2     .12       0  5252.9     .05       0  5651.4     .12       0
Bank Sta=4992,4996
XS Rating Curve= 0 ,0
Exp/Cntr=0.3,0.1

Type RM Length L Ch R = 1 ,13500   ,500,500,500
BEGIN DESCRIPTION:
COLORADO 01 27.0
END DESCRIPTION:
XS GIS Cut Line= 3
      2881905.64     10276153.12      2881278.09      10276229.6
      2880255.73     10276303.11
#Sta/Elev= 30
  4367.8 1123.45  4428.2 1121.43  4518.9 1119.95  4559.2 1118.69  4574.3 1117.27
  4629.7 1116.38    4656 1114.81  4690.1 1115.28  4737.6 1112.83  4742.6 1113.43
  4831.2 1111.51    4942 1106.66  4987.5 1101.88  4992.5 1102.11  4998.7  1100.3
  5010.4 1100.26  5010.7 1099.76  5014.4 1100.26  5042.5 1103.73  5082.6 1105.99
  5273.1 1114.85  5330.3 1116.13    5393 1117.88  5429.6 1117.66  5553.8 1119.67
    5634 1118.95  5764.4 1121.05  5914.8 1120.49    6015 1121.28    6025 1122.07
#Mann= 5 ,-1 , 0
  4367.8     .05       0  5010.4     .03       0  5014.4     .05       0
  5330.3     .12       0  5429.6     .05       0
Bank Sta=5010.4,5014.4
XS Rating Curve= 0 ,0
Exp/Cntr=0.3,0.1

Type RM Length L Ch R = 1 ,13000   ,500,500,500
BEGIN DESCRIPTION:
COLORADO 01 26.0
END DESCRIPTION:
XS GIS Cut Line= 3
      2881805.67      10276053.1      2881419.67     10275795.44
      2880555.69     10275703.11
#Sta/Elev= 30
  4535.9 1118.86    4604 1116.04  4678.2 1113.34  4708.6 1112.73  4719.4 1111.52
  4744.7 1110.24  4765.7 1110.25  4831.8 1105.15  4886.1 1103.21  4924.9 1101.37
  4939.9 1096.87  4945.9 1098.27  4954.9 1097.08  4960.9 1097.68    4995 1096.52
  4995.2 1096.02    4999 1096.52  5024.1    1099  5034.2 1097.29  5056.4 1098.98
  5074.4 1100.62  5144.8 1104.13  5161.5 1106.23  5254.1 1109.65  5376.1 1113.79
  5540.8 1114.72  5687.9 1117.33  5697.9 1118.29  5847.4 1120.27  5868.9 1120.36
#Mann= 10 ,-1 , 0
  4535.9     .05       0    4604     .12       0  4678.2     .05       0
  4719.4     .12       0  4886.1     .05       0    4995     .05       0
    4999     .05       0  5056.4     .12       0  5254.1     .05       0
  5847.4     .12       0
Bank Sta=4995,4999
XS Rating Curve= 0 ,0
Exp/Cntr=0.3,0.1

Type RM Length L Ch R = 1 ,12500   ,436,436,436
BEGIN DESCRIPTION:
COLORADO 01 25.0
END DESCRIPTION:
XS GIS Cut Line= 3
      2882005.68     10275553.11      2881524.42     10275354.05
      2880955.64     10275403.12
#Sta/Elev= 30
  4479.2 1114.77  4760.6 1103.16  4837.1 1101.92  4879.5 1098.68  4901.2 1098.95
  4908.8 1097.55  4932.7  1098.1  4938.1 1096.53    4962 1095.11  4967.4 1097.11
    4977 1097.42  4991.3 1095.11  4994.6 1092.49  4994.9 1091.99  4998.6 1092.49
  5045.6 1096.65  5089.1 1098.13  5189.4 1099.88  5277.3 1099.04  5319.9  1100.2
  5360.1 1103.35  5380.1 1103.45  5395.2 1106.52  5400.8 1106.09  5430.3 1109.98
  5450.4 1113.89  5490.6 1114.13  5514.2 1111.58  5540.7 1112.43  5570.9 1115.67
#Mann= 3 ,-1 , 0
  4479.2     .05       0  4994.6     .05       0  4998.6     .05       0
Bank Sta=4994.6,4998.6
XS Rating Curve= 0 ,0
Exp/Cntr=0.3,0.1

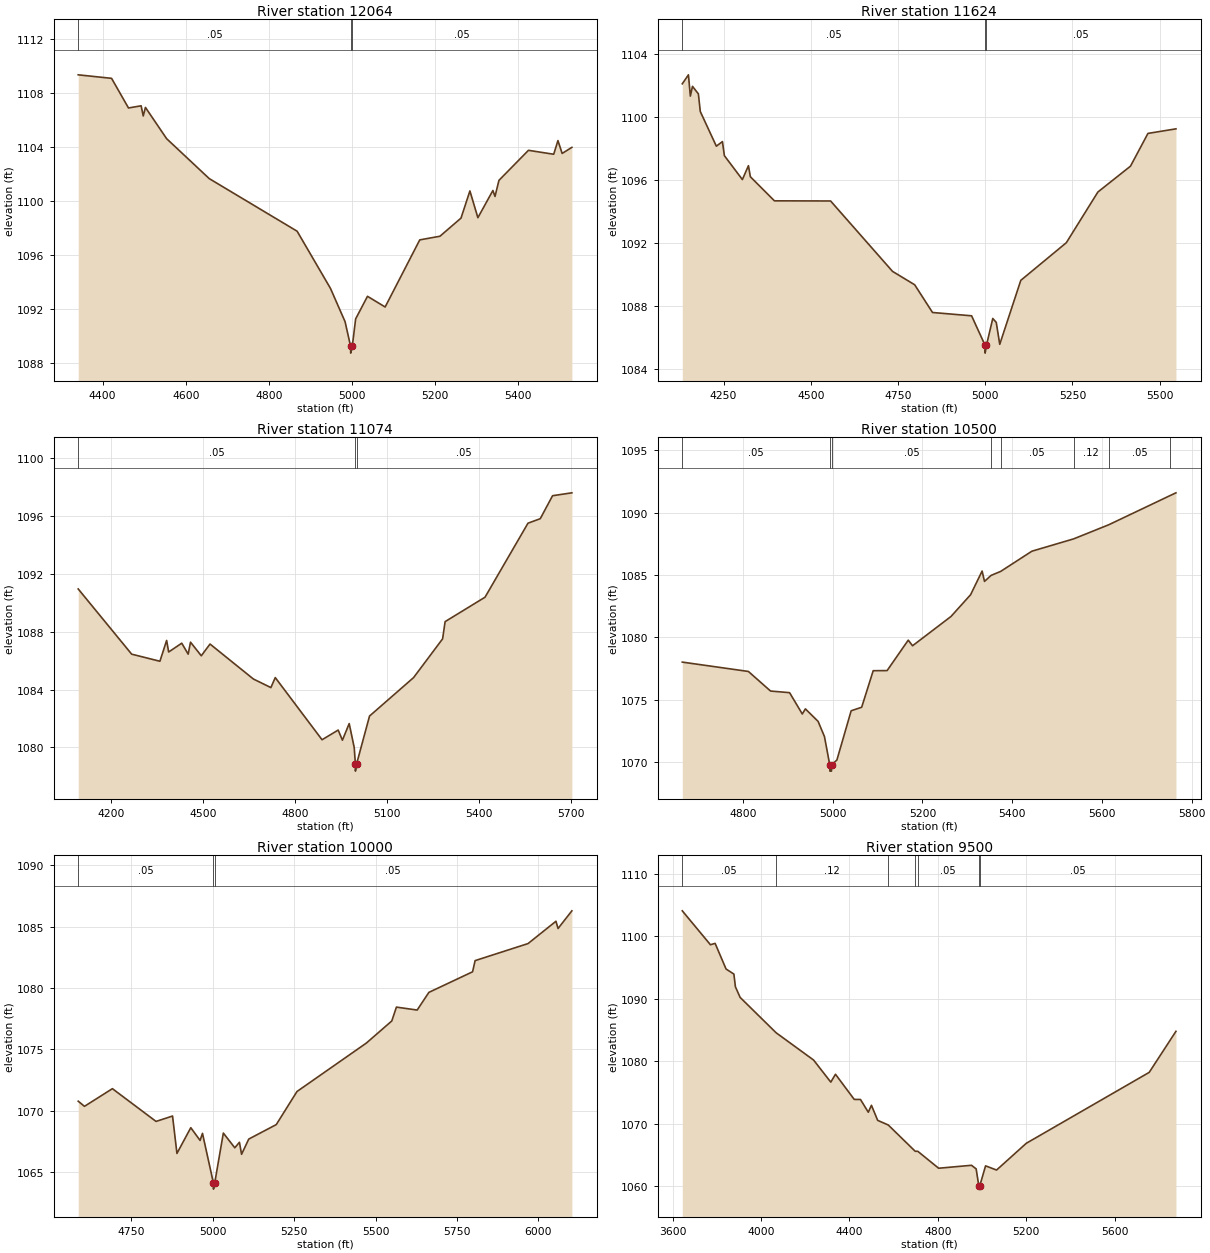
Type RM Length L Ch R = 1 ,12064   ,440,440,440
BEGIN DESCRIPTION:
Mapping XS e819a66a
END DESCRIPTION:
XS GIS Cut Line= 4
      2881984.43     10275098.42      2881589.49      10275020.3
      2881350.77      10274998.6      2880812.62     10275089.74
#Sta/Elev= 30
  4341.3 1109.33  4421.6 1109.07  4462.3 1106.88  4492.7 1107.04  4497.8 1106.29
  4503.1 1106.92  4554.1 1104.61  4656.6 1101.66  4868.2 1097.77  4948.5 1093.54
  4983.6 1091.08  4996.9 1089.26  4997.1 1088.76  5000.9 1089.26    5009 1091.29
  5037.5 1092.96    5080 1092.17  5163.3 1097.13  5211.9  1097.4  5262.6 1098.74
    5284 1100.75  5303.2 1098.77  5339.3 1100.78  5344.4 1100.34  5353.9 1101.53
  5424.9 1103.75  5485.7 1103.46  5495.9 1104.47    5506 1103.52  5529.4 1103.97
#Mann= 3 ,-1 , 0
  4341.3     .05       0  4996.9     .03       0  5000.9     .05       0
Bank Sta=4996.9,5000.9
XS Rating Curve= 0 ,0
Exp/Cntr=0.3,0.1

Type RM Length L Ch R = 1 ,11624   ,550,550,550
BEGIN DESCRIPTION:
Mapping XS 8ffebd10
END DESCRIPTION:
XS GIS Cut Line= 4
      2882032.24     10274907.47      2881407.19       10274621.
      2880916.74     10274577.59      2880686.68     10274625.34
#Sta/Elev= 30
  4131.6 1102.09  4149.2 1102.66  4154.7 1101.31  4160.8 1101.93  4177.7 1101.45
  4183.2 1100.33  4229.2 1098.13  4246.7 1098.42  4252.2 1097.53  4303.8 1096.01
  4321.2 1096.89  4326.7 1096.19  4395.7 1094.66  4556.7 1094.65  4734.2 1090.18
  4797.7 1089.33  4848.8 1087.57  4960.8 1087.36  4999.4 1085.49  4999.6 1084.99
  5003.4 1085.49  5021.5 1087.19  5031.5 1086.94  5041.5 1085.55  5101.8 1089.61
  5232.3    1092  5322.8 1095.22  5416.2 1096.86  5466.3 1098.94  5546.5 1099.23
#Mann= 3 ,-1 , 0
  4131.6     .05       0  4999.4     .03       0  5003.4     .05       0
Bank Sta=4999.4,5003.4
XS Rating Curve= 0 ,0
Exp/Cntr=0.3,0.1

Type RM Length L Ch R = 1 ,11074   ,574,574,574
BEGIN DESCRIPTION:
Mapping XS 2f49fd4c
END DESCRIPTION:
XS GIS Cut Line= 4
      2882092.98     10274681.78      2881567.79     10274221.69
      2881133.76       10273996.      2880712.78     10273982.98
#Sta/Elev= 30
  4093.5 1090.96  4267.7 1086.45  4359.7 1085.96  4381.6  1087.4  4388.2  1086.6
  4430.9 1087.21  4451.8 1086.45  4459.4 1087.28  4494.5 1086.34    4523 1087.15
  4664.4 1084.73  4721.3 1084.14  4735.6 1084.83    4888 1080.53  4940.6  1081.2
  4954.4  1080.5  4976.5 1081.65  4992.9 1079.99  4996.6 1078.86  4996.8 1078.36
  5000.6 1078.86  5042.8 1082.17  5186.3 1084.83  5280.9 1087.51    5289  1088.7
  5419.1 1090.39  5559.1 1095.51  5599.1 1095.82  5639.2 1097.41  5702.1 1097.61
#Mann= 3 ,-1 , 0
  4093.5     .05       0  4996.6     .03       0  5000.6     .05       0
Bank Sta=4996.6,5000.6
XS Rating Curve= 0 ,0
Exp/Cntr=0.3,0.1

Type RM Length L Ch R = 1 ,10500   ,500,500,500
BEGIN DESCRIPTION:
COLORADO 01 21.0
END DESCRIPTION:
XS GIS Cut Line= 3
      2881897.33     10273969.53      2881664.63     10273728.54
      2880942.81     10273475.17
#Sta/Elev= 30
    4665 1078.01  4812.3 1077.26  4861.7 1075.69  4904.1 1075.56  4932.4 1073.85
  4939.3 1074.26  4967.6 1073.26  4981.8 1072.04  4993.6 1069.77  4993.9 1069.27
  4997.4 1069.27  4997.6 1069.77  5009.5 1070.16  5041.3 1074.11  5064.7 1074.39
  5090.4 1077.32  5121.4 1077.33  5168.5 1079.77  5178.1 1079.32  5263.8 1081.67
  5307.4 1083.41  5333.1 1085.31  5338.4 1084.48  5353.1 1084.96  5374.4 1085.28
    5444  1086.9  5537.2 1087.89  5615.3 1089.02  5752.6 1091.37    5765 1091.58
#Mann= 8 ,-1 , 0
    4665     .05       0  4993.6     .03       0  4997.6     .05       0
  5353.1     .12       0  5374.4     .05       0  5537.2     .12       0
  5615.3     .05       0  5752.6     .12       0
Bank Sta=4993.6,4997.6
XS Rating Curve= 0 ,0
Exp/Cntr=0.3,0.1

Type RM Length L Ch R = 1 ,10000   ,500,500,500
BEGIN DESCRIPTION:
COLORADO 01 20.0
END DESCRIPTION:
XS GIS Cut Line= 3
      2882407.79     10273808.43      2882091.43     10273542.47
      2881250.97     10272828.48
#Sta/Elev= 30
  4586.7 1070.77  4605.9 1070.35  4691.7 1071.79  4825.7 1069.12  4876.4 1069.56
  4889.9 1066.51  4932.4 1068.61    4961 1067.57  4968.3 1068.15  5001.9  1064.1
  5002.1  1063.6  5005.9  1064.1  5032.4 1068.17  5067.6 1066.97  5081.8 1067.42
  5088.4 1066.44  5110.4 1067.68  5194.9 1068.86  5258.6 1071.56  5471.7 1075.51
  5549.7 1077.31    5564 1078.44  5627.7  1078.2  5663.6 1079.64  5797.9 1081.32
  5805.6 1082.23  5968.2 1083.62  6053.9 1085.44  6060.4 1084.85  6102.8 1086.29
#Mann= 3 ,-1 , 0
  4586.7     .05       0  5001.9     .05       0  5005.9     .05       0
Bank Sta=5001.9,5005.9
XS Rating Curve= 0 ,0
Exp/Cntr=0.3,0.1

Type RM Length L Ch R = 1 ,9500    ,500,500,500
BEGIN DESCRIPTION:
COLORADO 01 19.0
END DESCRIPTION:
XS GIS Cut Line= 3
      2883405.71     10274203.14      2882442.71     10273248.62
      2881755.65     10272703.09
#Sta/Elev= 30
  3644.1 1104.04  3771.4 1098.62  3792.6 1098.84  3842.1 1094.74  3877.5 1093.93
  3884.5 1091.89  3905.8  1090.2  4068.3 1084.56  4238.1 1080.19  4315.9 1076.66
  4337.1 1077.92  4421.9  1073.9  4450.2 1073.89  4485.6 1071.85  4499.8 1072.96
    4528 1070.55  4575.9 1069.81  4697.8 1065.61  4709.3 1065.61  4803.8  1062.9
  4952.3 1063.37  4973.5  1062.8  4985.6 1060.06  4985.9 1059.56  4989.6 1060.06
  5016.1 1063.28  5065.8 1062.61  5200.5 1066.89  5756.3 1078.22  5877.3 1084.78
#Mann= 7 ,-1 , 0
  3644.1     .05       0  4068.3     .12       0  4575.9     .05       0
  4697.8     .12       0  4709.3     .05       0  4985.6     .05       0
  4989.6     .05       0
Bank Sta=4985.6,4989.6
XS Rating Curve= 0 ,0
Exp/Cntr=0.3,0.1

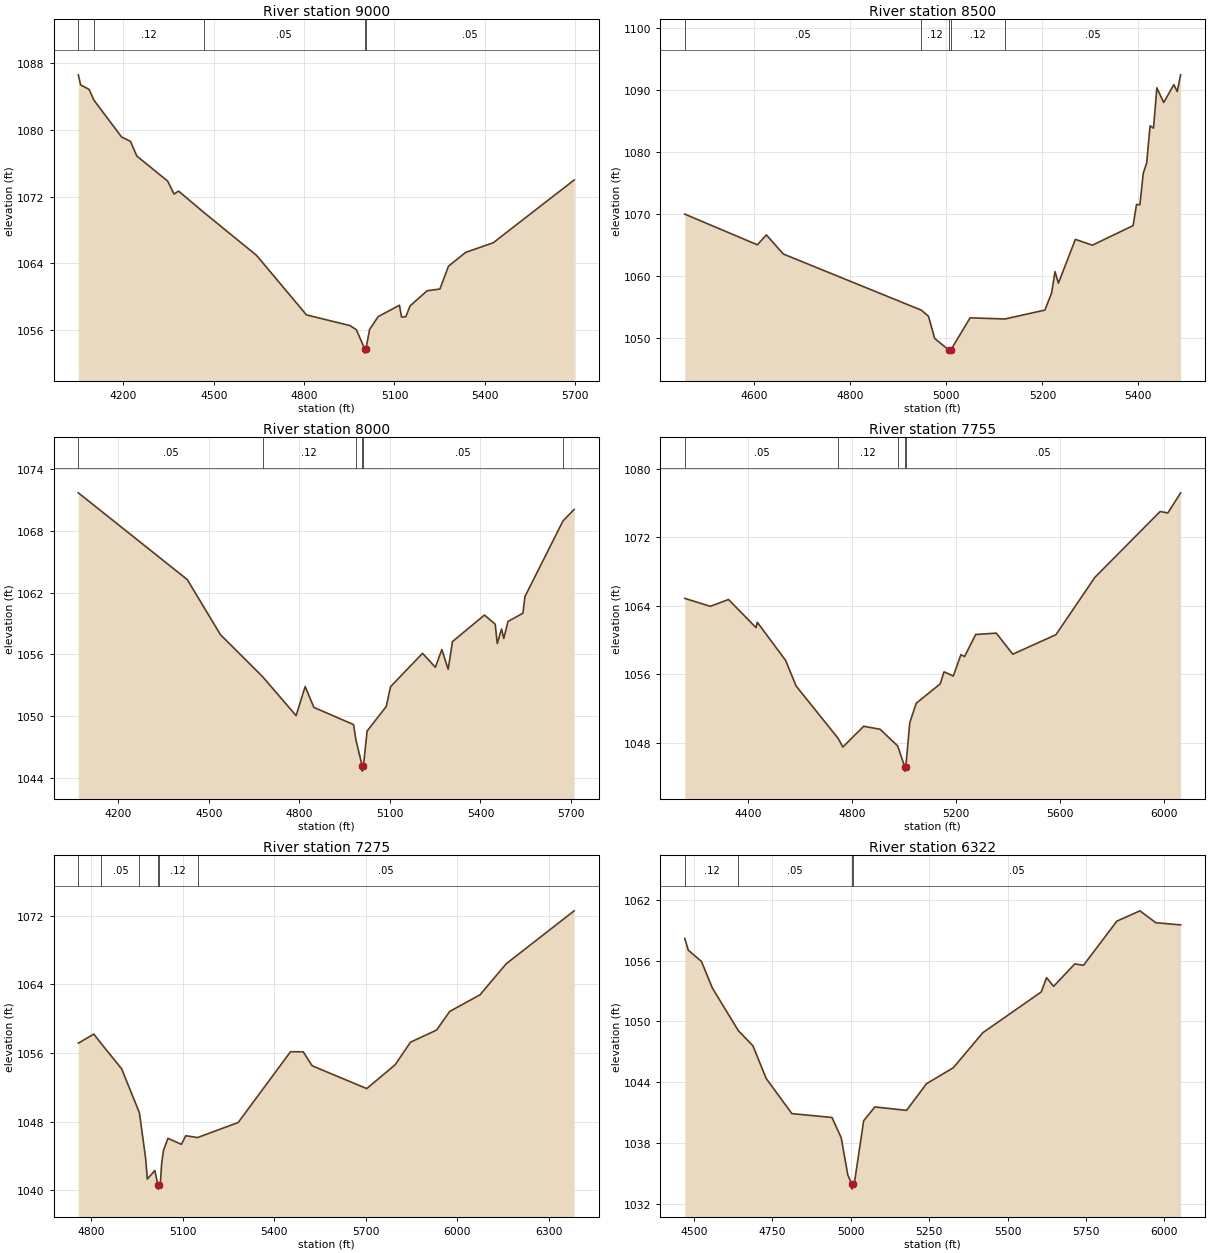
Type RM Length L Ch R = 1 ,9000    ,500,500,500
BEGIN DESCRIPTION:
COLORADO 01 18.0
END DESCRIPTION:
XS GIS Cut Line= 3
      2883355.67      10273753.1      2882833.25     10272960.12
      2882355.69     10272453.12
#Sta/Elev= 30
  4050.4 1086.58  4057.9 1085.38  4086.3 1084.83  4101.9 1083.56  4194.1 1079.13
  4223.5 1078.61  4244.6 1076.85    4347 1073.85  4368.1  1072.3  4383.2 1072.65
    4466 1070.13  4642.1 1064.95  4807.8 1057.82  4952.3 1056.54  4973.4 1056.04
  5001.2 1053.74  5001.5 1053.24  5005.2 1053.74  5017.4 1056.08  5045.7 1057.61
  5116.5 1058.98  5123.4 1057.57  5137.6  1057.6  5151.7  1058.9  5208.4 1060.71
  5250.9 1060.92  5279.2 1063.65  5335.8  1065.3  5427.7 1066.46  5696.5 1073.98
#Mann= 5 ,-1 , 0
  4050.4     .05       0  4101.9     .12       0    4466     .05       0
  5001.2     .05       0  5005.2     .05       0
Bank Sta=5001.2,5005.2
XS Rating Curve= 0 ,0
Exp/Cntr=0.3,0.1

Type RM Length L Ch R = 1 ,8500    ,500,500,500
BEGIN DESCRIPTION:
COLORADO 01 17.0
END DESCRIPTION:
XS GIS Cut Line= 3
      2883455.69     10273253.13       2883250.3     10272748.53
       2882905.7     10272403.13
#Sta/Elev= 30
  4455.2 1069.96  4606.4    1065  4625.1  1066.6  4660.4 1063.51  4947.8 1054.43
  4962.7 1053.45  4975.7 1049.85  5005.1 1047.98  5005.4 1047.48  5009.1 1047.98
  5049.5 1053.19    5122    1053  5205.1 1054.44  5219.2  1057.2  5226.3 1060.66
  5233.4  1058.8  5268.7 1065.88  5304.1 1064.94  5388.9  1068.1    5396 1071.52
  5403.1 1071.48  5410.1 1076.57  5417.2 1078.25  5424.3 1084.25  5431.4 1083.87
  5438.4 1090.39  5452.6 1088.01  5473.8  1090.9  5480.9 1089.79  5487.9 1092.49
#Mann= 5 ,-1 , 0
  4455.2     .05       0  4947.8     .12       0  5005.1     .07       0
  5009.1     .12       0    5122     .05       0
Bank Sta=5005.1,5009.1
XS Rating Curve= 0 ,0
Exp/Cntr=0.3,0.1

Type RM Length L Ch R = 1 ,8000    ,245,245,245
BEGIN DESCRIPTION:
COLORADO 01 16.0
END DESCRIPTION:
XS GIS Cut Line= 3
      2883555.68     10273303.08      2883490.27     10272372.67
      2883005.66     10271853.09
#Sta/Elev= 30
  4067.3  1071.7  4428.5 1063.27  4538.4 1057.92  4677.9 1053.85    4789 1050.06
  4819.1 1052.89  4847.9 1050.86  4979.5 1049.19  4986.8 1047.77  5008.1 1045.17
  5008.4 1044.67  5012.1 1045.17  5024.3 1048.56  5087.8 1050.95    5102 1052.87
    5208 1056.11  5250.5 1054.76    5272 1056.48    5293 1054.56  5307.2 1057.25
  5413.2 1059.83  5448.9 1058.94  5455.7 1057.06  5469.9 1058.48  5477.2 1057.56
  5491.4 1059.21  5540.7 1060.01  5547.5 1061.63  5673.7 1068.98  5710.5 1070.09
#Mann= 6 ,-1 , 0
  4067.3     .05       0  4677.9     .12       0  4986.8     .05       0
  5008.1     .05       0  5012.1     .05       0  5673.7     .12       0
Bank Sta=5008.1,5012.1
XS Rating Curve= 0 ,0
Exp/Cntr=0.3,0.1

Type RM Length L Ch R = 1 ,7755    ,480,480,480
BEGIN DESCRIPTION:
COLORADO 01 15.0
END DESCRIPTION:
XS GIS Cut Line= 3
      2883742.26     10273171.36      2883705.68     10272303.11
      2883105.71     10271453.15
#Sta/Elev= 30
  4156.2 1064.84  4254.5 1063.91  4324.6 1064.71  4430.5 1061.42  4435.5 1062.05
  4544.8 1057.58  4584.8 1054.61  4746.3  1048.5    4765 1047.48  4845.1  1049.9
  4908.3 1049.55  4976.1  1047.6  5003.2 1045.16  5003.4 1044.66  5007.2 1045.16
  5022.7 1050.34  5047.4 1052.59  5139.7 1054.85  5154.5 1056.26  5190.2 1055.77
  5219.8 1058.28  5233.3 1058.03  5276.4 1060.62  5355.7 1060.78  5419.2 1058.32
  5585.5  1060.6  5735.2 1067.29  5986.8 1074.99  6016.4 1074.82  6065.6 1077.17
#Mann= 5 ,-1 , 0
  4156.2     .05       0  4746.3     .12       0  4976.1     .05       0
  5003.2     .05       0  5007.2     .05       0
Bank Sta=5003.2,5007.2
XS Rating Curve= 0 ,0
Exp/Cntr=0.3,0.1

Type RM Length L Ch R = 1 ,7275    ,953,953,953
BEGIN DESCRIPTION:
COLORADO 01 14.0
END DESCRIPTION:
XS GIS Cut Line= 3
      2884202.34     10272650.52      2884105.68     10272403.11
      2883305.66     10271303.08
#Sta/Elev= 30
  4757.9 1057.14  4808.8  1058.2  4833.2 1057.08  4899.9 1054.15  4958.3 1049.01
  4978.7 1043.66  4984.1 1041.28  5008.6 1042.28  5018.8 1040.61  5019.1 1040.11
  5022.8 1040.61  5026.6 1040.61  5030.9 1043.04    5037 1044.62  5051.7 1046.04
  5095.8 1045.34  5110.1 1046.34  5148.8 1046.13    5282 1047.88  5453.6 1056.14
  5495.3 1056.13  5524.7  1054.5  5703.6 1051.84  5796.7 1054.62  5846.9 1057.25
  5932.7 1058.67  5975.6 1060.84  6074.9 1062.78  6161.1 1066.41  6383.7 1072.58
#Mann= 6 ,-1 , 0
  4757.9     .12       0  4833.2     .05       0  4958.3     .12       0
  5018.8     .07       0  5022.8     .12       0  5148.8     .05       0
Bank Sta=5018.8,5022.8
XS Rating Curve= 0 ,0
Exp/Cntr=0.3,0.1

Type RM Length L Ch R = 1 ,6322    ,360,360,360
BEGIN DESCRIPTION:
Mapping XS 86ac6294
END DESCRIPTION:
XS GIS Cut Line= 4
      2885083.41     10272442.17       2884909.8     10272029.85
      2884497.47     10271739.05      2883933.27     10271461.29
#Sta/Elev= 30
    4471 1058.19  4482.1 1057.04  4524.2 1055.92  4558.8 1053.31  4641.6  1049.1
  4688.3  1047.6  4730.3 1044.39  4812.4 1040.91  4940.3 1040.53  4969.8 1038.52
  4990.8 1034.85  5003.6 1033.96  5003.8 1033.46  5007.6 1033.96  5011.7 1034.06
  5041.3 1040.21    5077 1041.57    5178 1041.23  5241.6 1043.86  5327.2 1045.44
    5421 1048.89  5607.5 1052.92  5624.4 1054.32  5646.9 1053.47  5714.3 1055.68
  5742.3 1055.55  5848.5  1059.9    5922 1060.92  5972.6 1059.75  6051.8 1059.53
#Mann= 4 ,-1 , 0
    4471     .12       0  4641.6     .05       0  5003.6     .05       0
  5007.6     .05       0
Bank Sta=5003.6,5007.6
XS Rating Curve= 0 ,0
Exp/Cntr=0.3,0.1

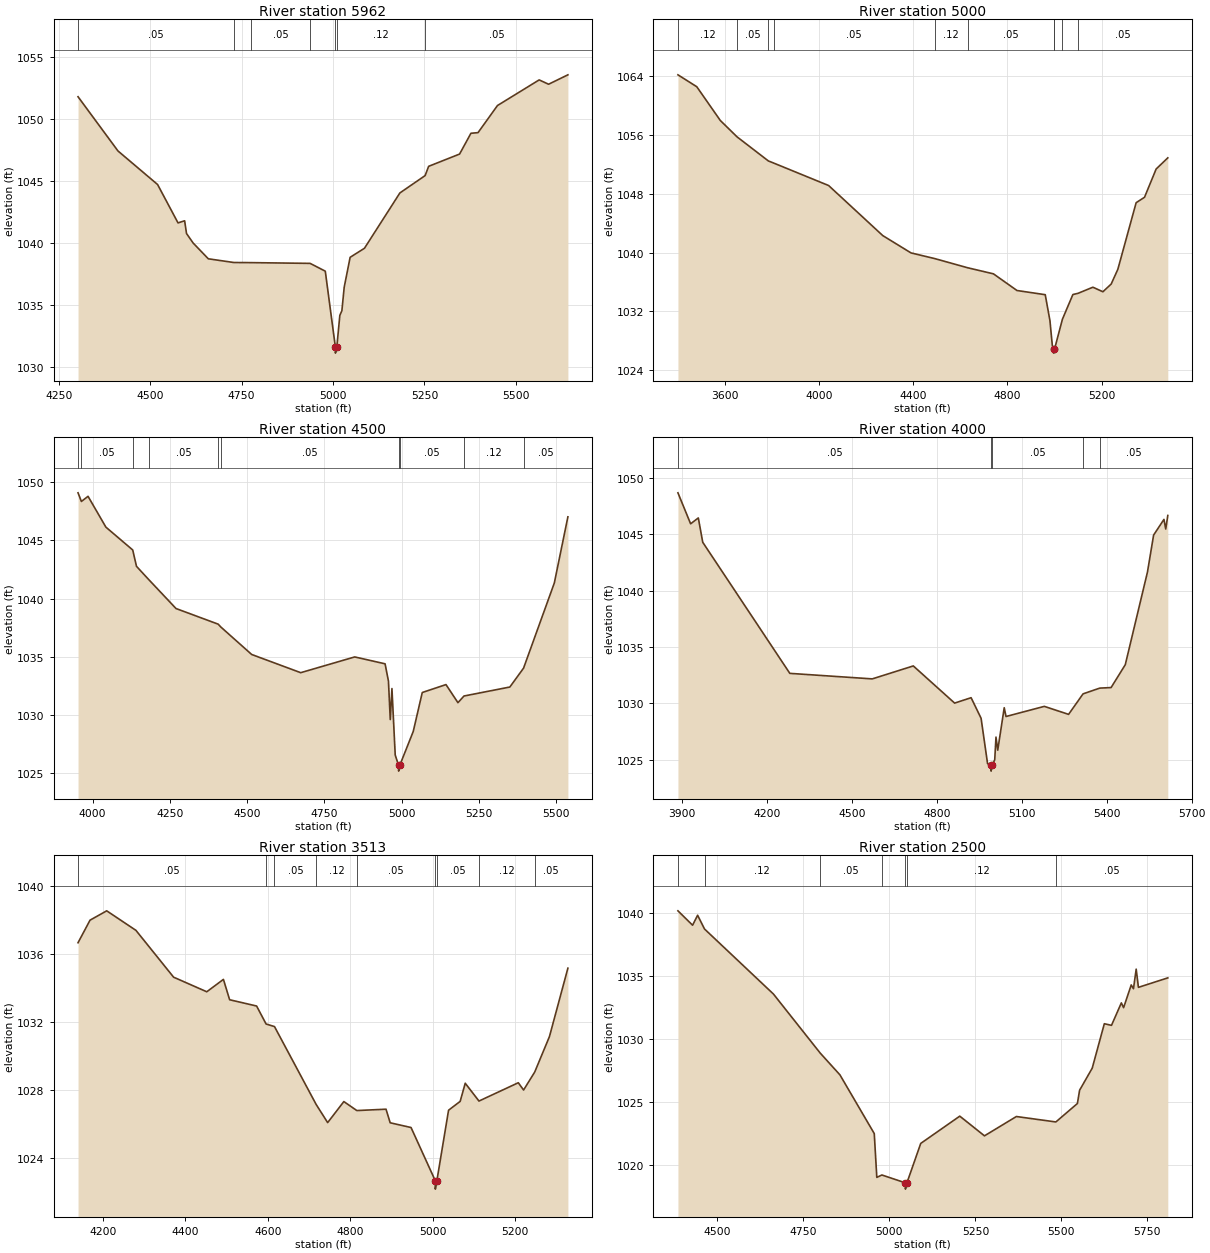
Type RM Length L Ch R = 1 ,5962    ,962,962,962
BEGIN DESCRIPTION:
Mapping XS 49cf30ed
END DESCRIPTION:
XS GIS Cut Line= 4
      2885278.73     10272246.89      2885135.49     10271726.03
      2884753.55     10271543.74      2884389.84     10271444.15
#Sta/Elev= 30
  4302.2  1051.8  4411.5 1047.42  4519.9 1044.71  4575.8 1041.61  4593.9 1041.78
  4599.1 1040.75  4617.3 1039.98  4658.7 1038.71  4728.4 1038.41    4775  1038.4
  4937.3 1038.34  4978.8 1037.71  5006.4 1031.59  5006.6 1031.09  5010.4 1031.59
  5018.6 1034.14  5024.2 1034.51  5030.6 1036.42  5046.8 1038.83    5086 1039.56
    5183 1044.03    5252 1045.43  5261.7 1046.18  5346.3 1047.17  5377.4 1048.85
  5396.8  1048.9    5450 1051.09  5564.1 1053.16  5589.9 1052.81  5642.7 1053.57
#Mann= 7 ,-1 , 0
  4302.2     .05       0  4728.4     .12       0    4775     .05       0
  4937.3     .12       0  5006.4     .07       0  5010.4     .12       0
    5252     .05       0
Bank Sta=5006.4,5010.4
XS Rating Curve= 0 ,0
Exp/Cntr=0.3,0.1

Type RM Length L Ch R = 1 ,5000    ,500,500,500
BEGIN DESCRIPTION:
COLORADO 01 10.0
END DESCRIPTION:
XS GIS Cut Line= 3
      2885555.68     10272753.09      2885585.34     10271153.96
       2885255.7     10270803.13
#Sta/Elev= 30
  3400.6 1064.22  3480.6  1062.6  3580.6    1058  3651.7 1055.77  3784.7 1052.49
  3808.1 1052.19  4040.7 1049.14  4270.7 1042.32  4390.7 1039.96  4491.2 1039.19
    4631 1037.94  4740.8 1037.11  4840.8 1034.84  4960.8 1034.27  4980.8 1030.73
  4990.8 1027.37  4995.9 1026.81  4996.2 1026.31  4999.9 1026.81  5033.8 1030.93
  5078.2 1034.29  5100.4 1034.46  5163.2 1035.29  5205.7 1034.67  5240.9 1035.72
  5269.2 1037.73  5346.9  1046.8  5382.5 1047.54  5431.9 1051.39  5481.4 1052.91
#Mann= 10 ,-1 , 0
  3400.6     .12       0  3651.7     .05       0  3784.7     .12       0
  3808.1     .05       0  4491.2     .12       0    4631     .05       0
  4995.9     .03       0  4999.9     .05       0  5033.8     .12       0
  5100.4     .05       0
Bank Sta=4995.9,4999.9
XS Rating Curve= 0 ,0
Exp/Cntr=0.3,0.1

Type RM Length L Ch R = 1 ,4500    ,500,500,500
BEGIN DESCRIPTION:
COLORADO 01 9.0
END DESCRIPTION:
XS GIS Cut Line= 3
      2885605.67     10272153.14      2886025.25     10271194.11
      2885805.67     10270703.07
#Sta/Elev= 30
  3953.2 1049.06  3964.1 1048.32  3985.6 1048.76  4043.3 1046.12  4130.1 1044.16
  4142.3 1042.76  4181.3 1041.64  4270.2 1039.14  4406.6  1037.8    4415 1037.56
    4515  1035.2  4673.6 1033.64  4848.3 1034.99  4946.5  1034.4  4957.4 1032.92
  4963.3 1029.62  4968.7 1032.28  4979.3 1026.58  4990.1  1025.7  4990.4  1025.2
  4994.1  1025.7  5037.6  1028.6  5066.8 1031.94  5143.5 1032.62  5182.2 1031.07
  5201.8 1031.64  5350.1 1032.41  5394.5 1034.03    5494 1041.33  5537.9    1047
#Mann= 10 ,-1 , 0
  3953.2     .12       0  3964.1     .05       0  4130.1     .12       0
  4181.3     .05       0  4406.6     .12       0    4415     .05       0
  4990.1     .03       0  4994.1     .05       0  5201.8     .12       0
  5394.5     .05       0
Bank Sta=4990.1,4994.1
XS Rating Curve= 0 ,0
Exp/Cntr=0.3,0.1

Type RM Length L Ch R = 1 ,4000    ,487,487,487
BEGIN DESCRIPTION:
COLORADO 01 8.0
END DESCRIPTION:
XS GIS Cut Line= 3
       2885905.7     10272053.09      2886475.91     10271095.04
      2886105.67      10270603.1
#Sta/Elev= 30
  3885.1 1048.69  3929.9 1045.94  3957.1 1046.46  3972.7  1044.3  4280.4 1032.66
  4571.7 1032.17  4716.6 1033.32  4862.6 1030.02  4920.8  1030.5  4956.1 1028.67
    4979 1024.64  4991.1 1024.48  4991.4 1023.98  4995.1 1024.48  5004.3 1024.99
  5008.7    1027  5014.9 1025.84  5037.8 1029.61  5044.1 1028.83  5179.4 1029.73
  5265.2 1029.02  5316.3 1030.84  5375.2 1031.35  5415.4  1031.4  5465.5 1033.43
  5543.8 1041.65  5565.6 1044.94  5602.1 1046.33  5608.4 1045.48  5615.7 1046.68
#Mann= 5 ,-1 , 0
  3885.1     .05       0  4991.1     .03       0  4995.1     .05       0
  5316.3     .12       0  5375.2     .05       0
Bank Sta=4991.1,4995.1
XS Rating Curve= 0 ,0
Exp/Cntr=0.3,0.1

Type RM Length L Ch R = 1 ,3513    ,1013,1013,1013
BEGIN DESCRIPTION:
Mapping XS 50d21cd3
END DESCRIPTION:
XS GIS Cut Line= 2
      2886728.37     10271851.94      2886897.48     10270676.85
#Sta/Elev= 30
  4140.2 1036.66  4169.3 1037.99  4209.7 1038.54  4280.5 1037.39  4371.8 1034.63
  4452.2 1033.77  4492.6  1034.5  4507.6  1033.3    4573 1032.93    4596 1031.87
  4616.3 1031.72  4717.3 1027.13  4745.2 1026.06  4784.4  1027.3  4815.9 1026.77
  4886.6 1026.85  4896.7 1026.05  4947.3 1025.77  5005.9 1022.64  5006.1 1022.14
  5009.9 1022.64  5038.2 1026.79  5066.3 1027.31  5078.6 1028.38  5111.9 1027.33
  5207.2 1028.41    5220 1027.98    5247 1029.04  5282.7 1031.13  5327.4 1035.16
#Mann= 9 ,-1 , 0
  4140.2     .05       0    4596     .12       0  4616.3     .05       0
  4717.3     .12       0  4815.9     .05       0  5005.9     .03       0
  5009.9     .05       0  5111.9     .12       0    5247     .05       0
Bank Sta=5005.9,5009.9
XS Rating Curve= 0 ,0
Exp/Cntr=0.3,0.1

Type RM Length L Ch R = 1 ,2500    ,718,718,718
BEGIN DESCRIPTION:
COLORADO 01 5.0
END DESCRIPTION:
XS GIS Cut Line= 3
      2888105.69     10271603.12      2887733.39       10271114.
      2887105.71     10270603.13
#Sta/Elev= 30
  4385.3 1040.14  4427.9    1039  4442.5 1039.79  4462.6  1038.7  4662.9 1033.55
  4798.7 1028.88  4856.2 1027.15    4956  1022.5  4963.4 1019.03  4978.1 1019.22
  5046.2  1018.6  5046.6  1018.1    5051  1018.6  5091.1 1021.72  5204.6 1023.88
  5276.4 1022.32  5369.1 1023.85  5483.9 1023.42  5546.5 1024.88  5552.9 1025.93
  5589.6 1027.68  5624.8  1031.2  5645.6 1031.07  5674.3 1032.85  5680.8 1032.47
    5703 1034.27  5709.5 1033.97  5717.4 1035.52  5723.9 1034.08  5809.3 1034.83
#Mann= 7 ,-1 , 0
  4385.3     .05       0  4462.6     .12       0  4798.7     .05       0
  4978.1     .12       0  5046.2     .07       0    5051     .12       0
  5483.9     .05       0
Bank Sta=5046.2,5051
XS Rating Curve= 0 ,0
Exp/Cntr=0.3,0.1

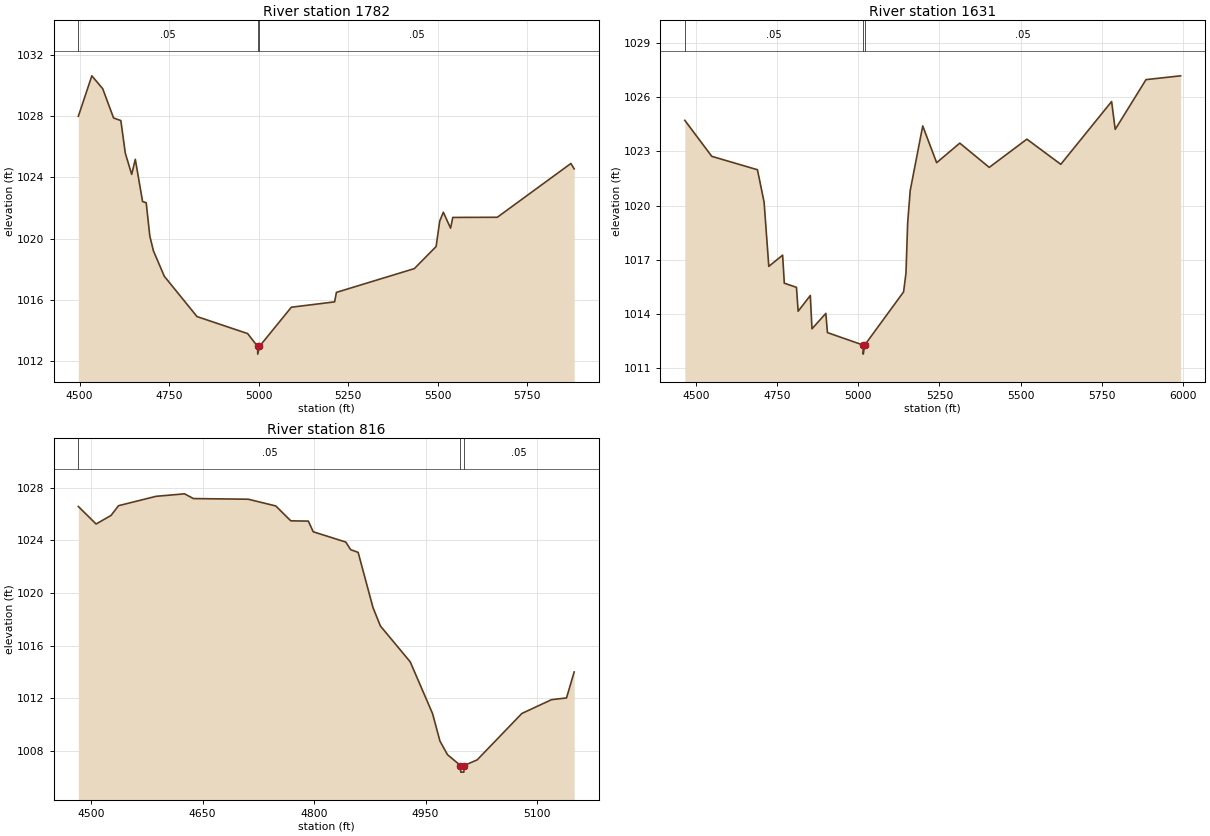
Type RM Length L Ch R = 1 ,1782    ,151,151,151
BEGIN DESCRIPTION:
Mapping XS deca7d0d
END DESCRIPTION:
XS GIS Cut Line= 4
        2888803.     10270827.59      2888264.83     10270745.13
      2887761.36       10270667.      2887431.52      10270688.7
#Sta/Elev= 30
  4496.5 1027.98  4534.2 1030.62  4564.6 1029.78  4594.9 1027.87  4615.2  1027.7
  4627.7 1025.57  4645.5 1024.19  4655.6 1025.17  4675.9 1022.42    4686 1022.34
  4696.1 1020.17  4706.2  1019.2  4736.6 1017.54  4827.9 1014.91  4969.3  1013.8
  4997.2 1012.96  4997.5 1012.46  5002.1 1012.96  5091.2 1015.52  5212.1 1015.87
  5217.2 1016.49  5434.7 1018.04  5495.5 1019.48  5505.6 1021.14  5515.7 1021.72
  5535.9 1020.68  5542.1 1021.38  5666.4 1021.39  5871.9  1024.9    5881 1024.55
#Mann= 3 ,-1 , 0
  4496.5     .05       0  4997.2     .03       0  5002.1     .05       0
Bank Sta=4997.2,5002.1
XS Rating Curve= 0 ,0
Exp/Cntr=0.3,0.1

Type RM Length L Ch R = 1 ,1631    ,815,815,815
BEGIN DESCRIPTION:
Mapping XS e8dc2c2e
END DESCRIPTION:
XS GIS Cut Line= 5
      2888863.78     10270736.45      2888377.68      10270623.6
      2888000.08     10270549.82      2887683.24     10270528.11
      2887375.04     10270636.63
#Sta/Elev= 30
  4465.3 1024.71  4548.5 1022.72  4689.2 1021.98  4709.7 1020.19  4724.2 1016.64
  4766.8 1017.26    4772 1015.71  4809.5 1015.48  4814.6 1014.16  4852.1 1015.03
  4857.3 1013.19  4899.9 1014.04    4905 1012.98  5014.9 1012.29  5015.2 1011.79
  5019.8 1012.29  5139.6 1015.23    5147 1016.28  5152.1 1019.02    5160 1020.83
  5198.6  1024.4  5241.5 1022.37  5312.8 1023.45  5403.6 1022.11  5519.6 1023.67
  5624.1 1022.28  5780.7 1025.75  5791.8 1024.21  5886.7 1026.96  5993.4 1027.17
#Mann= 3 ,-1 , 0
  4465.3     .05       0  5014.9     .03       0  5019.8     .05       0
Bank Sta=5014.9,5019.8
XS Rating Curve= 0 ,0
Exp/Cntr=0.3,0.1

Type RM Length L Ch R = 1 ,816     ,0,0,0
BEGIN DESCRIPTION:
Mapping XS 7fe361a4
END DESCRIPTION:
XS GIS Cut Line= 3
      2889028.72     10270766.81      2888984.26     10270409.69
      2888967.96      10270102.8
#Sta/Elev= 30
  4482.7 1026.56  4506.6 1025.23  4526.7 1025.88  4536.8 1026.62  4587.2 1027.33
  4625.6 1027.52  4637.6 1027.16  4711.4 1027.11  4748.4  1026.6  4768.6 1025.47
  4792.2 1025.45  4798.8 1024.64  4842.6 1023.86  4849.2 1023.28  4859.2 1023.08
  4879.2 1018.89  4889.2 1017.49  4929.3 1014.77  4959.3 1010.85  4969.3 1008.76
  4979.4 1007.73  4996.9  1006.9  4997.3  1006.4  5001.5  1006.4  5001.8  1006.9
  5019.4 1007.33  5079.5 1010.85  5119.5  1011.9  5139.6 1012.03  5149.9    1014
#Mann= 3 ,-1 , 0
  4482.7     .05       0  4996.9     .03       0  5001.8     .05       0
Bank Sta=4996.9,5001.8
XS Rating Curve= 0 ,0
Exp/Cntr=0.3,0.1

Chan Stop Cuts=-1
Use User Specified Reach Order=0