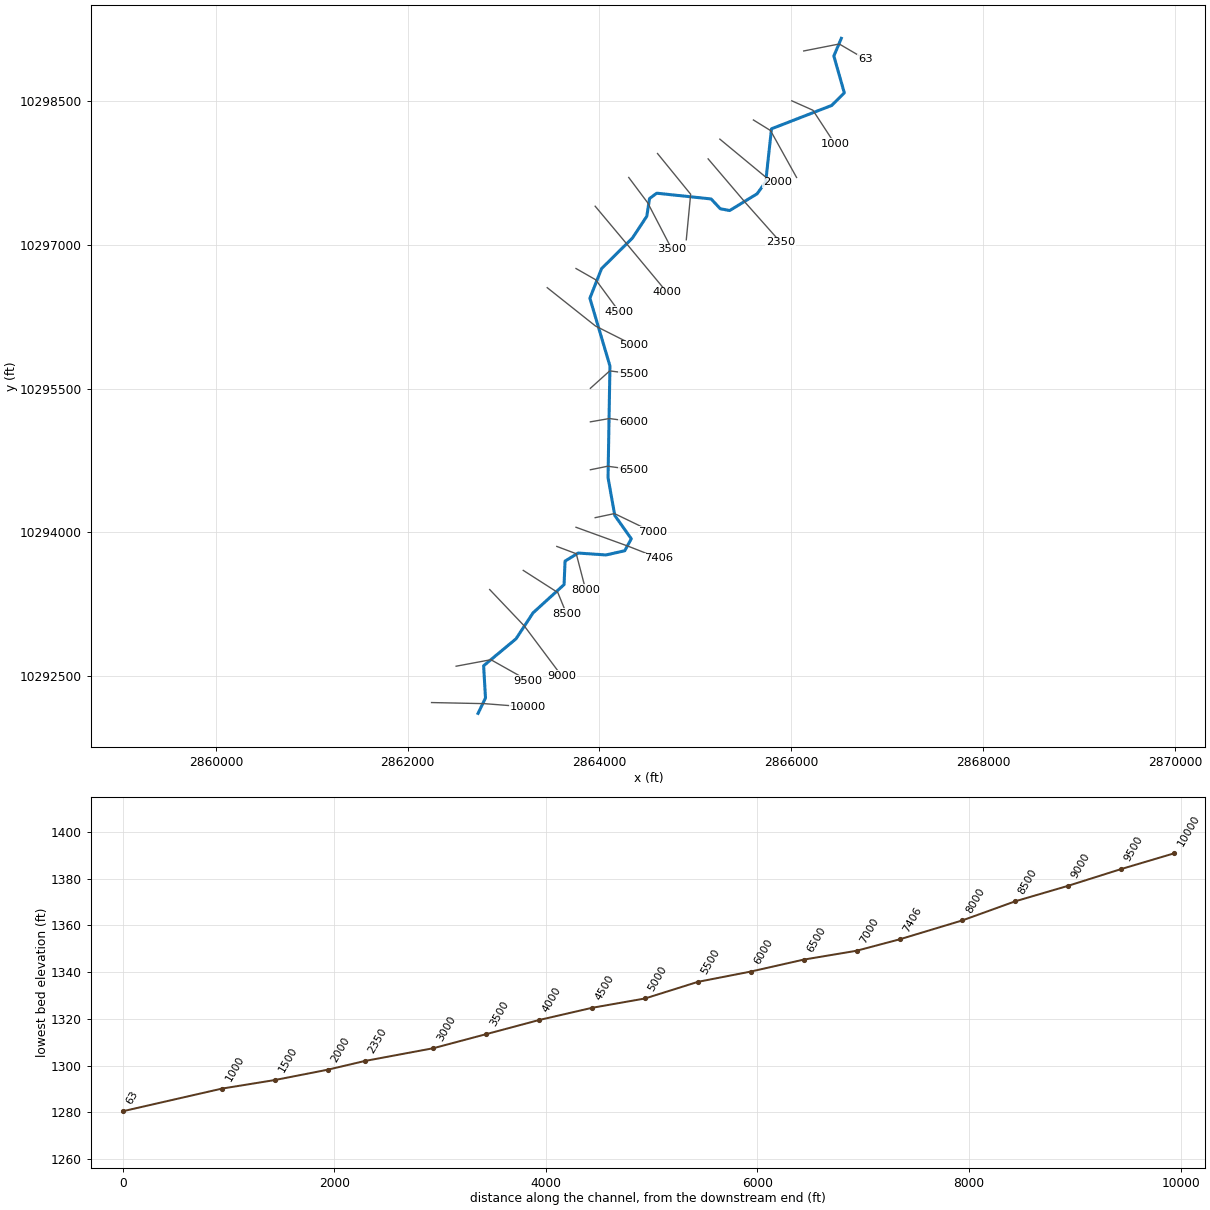
--- COLORADO 04.prj (project) ---

Proj Title=COLORADO 04 Base Level Engineering
Current Plan=p01
Default Exp/Contr=0.3,0.1
English Units
Geom File=g01
Flow File=f01
Plan File=p01
Y Axis Title=Elevation
X Axis Title(PF)=Main Channel Distance
X Axis Title(XS)=Station
BEGIN DESCRIPTION:
COLORADO 04
END DESCRIPTION:
DSS Export Rating Curves= 0
DSS Export Rating Curve Sorted= 0
DSS Export Volume Flow Curves= 0
DXF OffsetX= 0
DXF OffsetY= 0
DXF ScaleX= 1
DXF ScaleY= 10

--- COLORADO 04.p01 (plan) ---

Plan Title=Multiple Run
Short Identifier=Multiple
Geom File=g01
Flow File=f01
Subcritical Flow
K Sum by GR= 0
Std Step Tol= 0.01
Critical Tol= 0.01
Num of Std Step Trials= 20
Max Error Tol= 0.3
Flow Tol Ratio= 0.001
Split Flow NTrial= 30
Split Flow Tol= 0.02
Split Flow Ratio= 0.02
Log Output Level= 0
Friction Slope Method= 1
Unsteady Friction Slope Method= 2
Unsteady Bridges Friction Slope Method= 1
Parabolic Critical Depth
Global Vel Dist=  1 , 1 , 1
Global Log Level= 0
CheckData=True
Encroach Param= -1, 0, 0, 0
BEGIN DESCRIPTION:
Multiple Run
END DESCRIPTION:

--- COLORADO 04.f01 (steady flow) ---

Flow Title=Multiple
Number of Profiles=7
Profile Names=10-year,25-year,50-year,1pct_min,100-year,1pct_plu,500-year
River Rch & RM= COLORADO 04,Reach-1,10000
     356     568     815     634    1088    1869    1510
River Rch & RM= COLORADO 04,Reach-1,5000
     696    1159    1707    1263    2327    4287    3203
Boundary for River Rch & Prof#=COLORADO 04,Reach-1,1
Up Type=0
Dn Type=3
Dn Slope=0.005
Boundary for River Rch & Prof#=COLORADO 04,Reach-1,2
Up Type=0
Dn Type=3
Dn Slope=0.005
Boundary for River Rch & Prof#=COLORADO 04,Reach-1,3
Up Type=0
Dn Type=3
Dn Slope=0.005
Boundary for River Rch & Prof#=COLORADO 04,Reach-1,4
Up Type=0
Dn Type=3
Dn Slope=0.005
Boundary for River Rch & Prof#=COLORADO 04,Reach-1,5
Up Type=0
Dn Type=3
Dn Slope=0.005
Boundary for River Rch & Prof#=COLORADO 04,Reach-1,6
Up Type=0
Dn Type=3
Dn Slope=0.005
Boundary for River Rch & Prof#=COLORADO 04,Reach-1,7
Up Type=0
Dn Type=3
Dn Slope=0.005

--- COLORADO 04.g01 (geometry) ---

Geom Title=Existing Conditions

River Reach=COLORADO 04,Reach-1
Reach XY= 30
      2862734.50     10292111.00      2862812.00     10292272.00
      2862792.50     10292608.00      2863130.25     10292889.00
      2863308.00     10293160.00      2863631.50     10293455.00
      2863641.50     10293700.00      2863778.25     10293784.00
      2864068.75     10293764.00      2864264.00     10293808.00
      2864332.00     10293933.00      2864160.25     10294176.00
      2864089.75     10294571.00      2864109.75     10295736.00
      2863900.50     10296443.00      2864022.25     10296752.00
      2864344.25     10297071.00      2864494.25     10297299.00
      2864522.25     10297483.00      2864597.25     10297539.00
      2865164.75     10297479.00      2865259.75     10297377.00
      2865358.00     10297358.00      2865644.25     10297533.00
      2865734.00     10297658.00      2865794.25     10298211.00
      2866422.25     10298455.00      2866553.50     10298586.00
      2866444.25     10298971.00      2866522.25     10299155.00

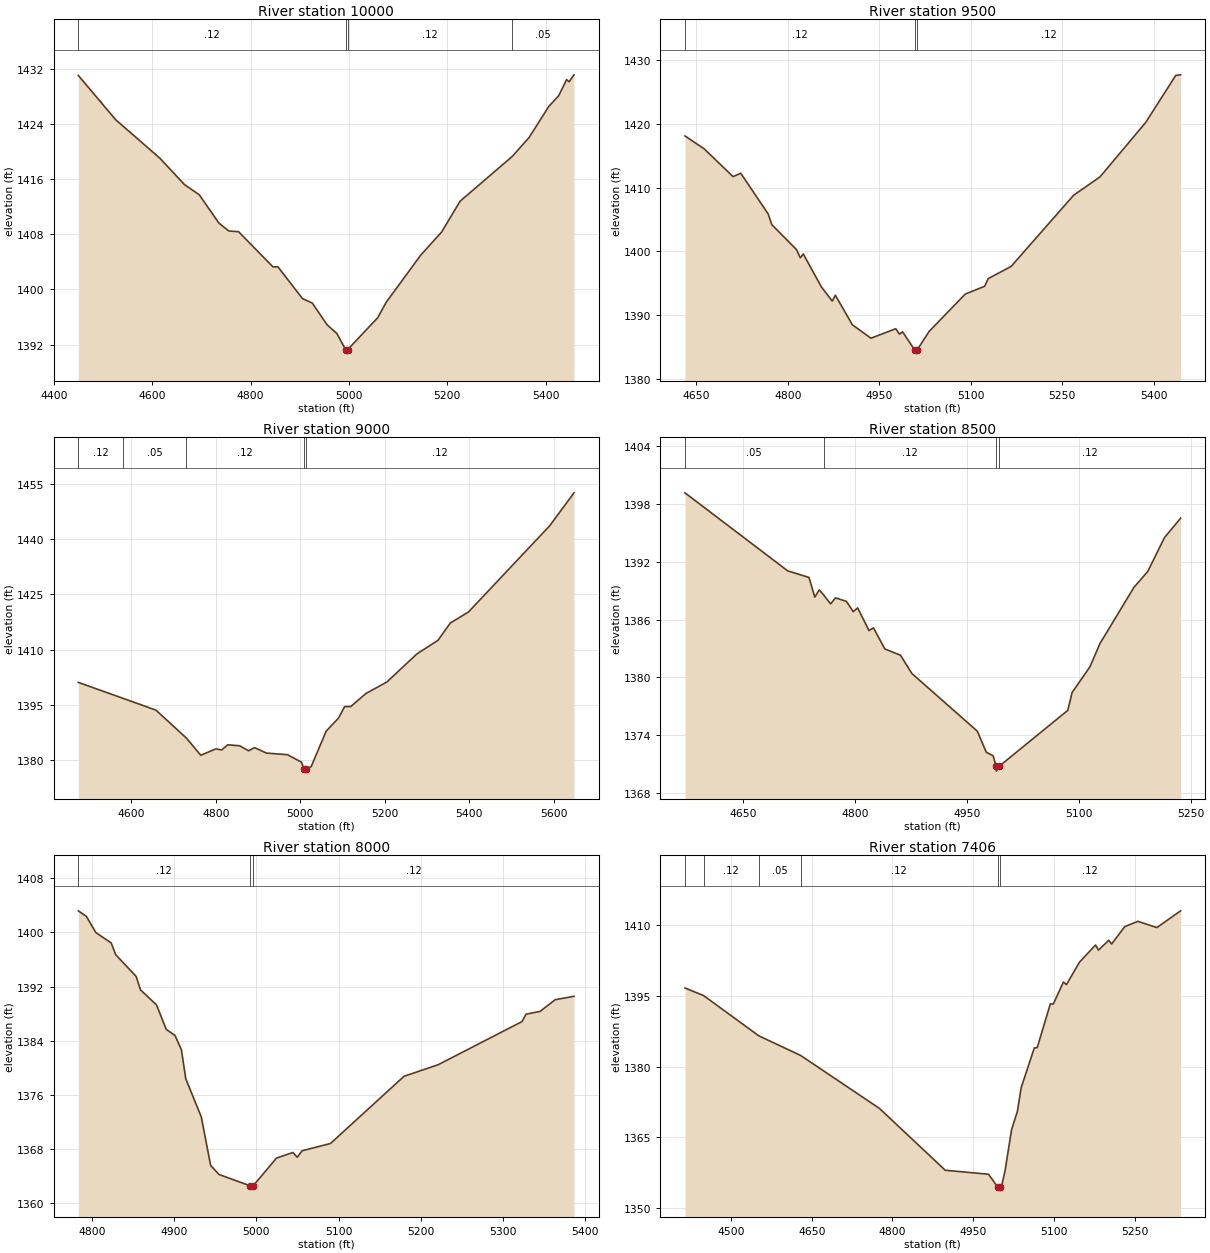
Type RM Length L Ch R = 1,10000,500,500,500
BEGIN DESCRIPTION:
COLORADO 04 20.0
END DESCRIPTION:
XS GIS Cut Line= 3
      2862249.68     10292223.88      2862800.16     10292212.51
      2863256.69     10292177.04
#Sta/Elev= 30
  4449.4 1431.04  4525.4 1424.62  4615.4 1419.03  4665.4 1415.21  4695.5 1413.73
  4735.5 1409.62  4755.5 1408.48  4775.5 1408.37  4845.5 1403.27  4855.5 1403.28
  4905.5 1398.67  4925.5 1398.02  4955.5 1394.88  4975.5 1393.60  4993.3 1391.26
  4993.5 1390.76  4997.0 1390.76  4997.3 1391.26  5058.7 1395.91  5075.7 1398.12
  5146.0 1404.97  5188.5 1408.32  5226.2 1412.80  5332.3 1419.29  5366.6 1422.04
  5406.7 1426.55  5426.8 1428.10  5443.0 1430.44  5448.0 1430.12  5457.9 1431.13
#Mann=4,-1,0
  4449.4    0.12       0  4993.3    0.07       0  4997.3    0.12       0
  5332.3    0.05       0
Bank Sta=4993.3,4997.3
Exp/Cntr=0.3,0.1

Type RM Length L Ch R = 1,9500,500,500,500
BEGIN DESCRIPTION:
COLORADO 04 19.0
END DESCRIPTION:
XS GIS Cut Line= 3
      2862505.68     10292603.11      2862868.27     10292671.04
      2863255.68     10292453.11
#Sta/Elev= 30
  4631.1 1418.12  4662.5 1416.11  4710.0 1411.74  4722.7 1412.27  4767.7 1405.87
  4773.5 1404.22  4814.2 1400.28  4820.3 1399.01  4825.3 1399.61  4854.9 1394.45
  4872.8 1392.21  4877.9 1393.13  4905.8 1388.50  4936.3 1386.39  4977.0 1387.88
  4983.1 1387.02  4988.2 1387.39  5008.1 1384.55  5008.4 1384.05  5012.1 1384.55
  5031.8 1387.46  5091.1 1393.32  5122.9 1394.54  5128.7 1395.74  5166.3 1397.65
  5268.9 1408.82  5312.2 1411.70  5387.1 1420.23  5436.5 1427.62  5444.5 1427.71
#Mann=3,-1,0
  4631.1    0.12       0  5008.1    0.07       0  5012.1    0.12       0
Bank Sta=5008.1,5012.1
Exp/Cntr=0.3,0.1

Type RM Length L Ch R = 1,9000,500,500,500
BEGIN DESCRIPTION:
COLORADO 04 18.0
END DESCRIPTION:
XS GIS Cut Line= 3
      2862855.66     10293403.14      2863217.57     10293022.12
      2863605.70     10292503.10
#Sta/Elev= 30
  4474.5 1401.06  4580.4 1396.72  4658.4 1393.50  4730.6 1385.88  4764.4 1381.22
  4799.9 1382.95  4814.1 1382.68  4828.3 1384.07  4856.6 1383.80  4877.6 1382.44
  4891.8 1383.30  4920.1 1381.81  4969.8 1381.38  5002.5 1379.36  5009.4 1377.40
  5009.6 1376.90  5013.4 1377.40  5025.9 1378.15  5061.4 1387.79  5090.6 1391.35
  5105.1 1394.47  5119.7 1394.49  5155.2 1398.02  5205.2 1401.18  5276.0 1408.80
  5326.1 1412.52  5355.3 1417.22  5398.3 1420.24  5590.8 1443.73  5648.1 1452.68
#Mann=5,-1,0
  4474.5    0.12       0  4580.4    0.05       0  4730.6    0.12       0
  5009.4    0.07       0  5013.4    0.12       0
Bank Sta=5009.4,5013.4
Exp/Cntr=0.3,0.1

Type RM Length L Ch R = 1,8500,500,500,500
BEGIN DESCRIPTION:
COLORADO 04 17.0
END DESCRIPTION:
XS GIS Cut Line= 3
      2863205.69     10293603.11      2863566.01     10293372.12
      2863655.70     10293153.07
#Sta/Elev= 30
  4572.0 1399.15  4709.8 1391.05  4738.3 1390.37  4746.1 1388.33  4752.1 1389.08
  4757.9 1388.56  4767.3 1387.63  4773.9 1388.25  4788.4 1387.89  4797.7 1386.82
  4803.6 1387.21  4818.8 1384.85  4824.8 1385.14  4840.0 1382.95  4861.1 1382.29
  4876.3 1380.40  4964.0 1374.42  4976.1 1372.23  4985.3 1371.86  4989.3 1370.77
  4989.5 1370.27  4993.3 1370.77  5085.4 1376.58  5091.1 1378.42  5115.1 1381.10
  5128.6 1383.52  5174.0 1389.33  5192.6 1390.99  5215.0 1394.50  5236.7 1396.52
#Mann=4,-1,0
  4572.0    0.05       0  4757.9    0.12       0  4989.3    0.07       0
  4993.3    0.12       0
Bank Sta=4989.3,4993.3
Exp/Cntr=0.3,0.1

Type RM Length L Ch R = 1,8000,594,594,594
BEGIN DESCRIPTION:
COLORADO 04 16.0
END DESCRIPTION:
XS GIS Cut Line= 3
      2863555.65     10293853.12      2863758.38     10293776.86
      2863855.68     10293403.12
#Sta/Elev= 30
  4783.4 1403.19  4793.2 1402.37  4804.8 1399.97  4823.4 1398.45  4828.8 1396.72
  4853.7 1393.51  4859.0 1391.52  4878.5 1389.30  4890.3 1385.69  4901.0 1384.78
  4908.8 1382.67  4914.1 1378.38  4933.0 1372.75  4944.3 1365.61  4954.4 1364.27
  4992.1 1362.60  4992.4 1362.10  4996.1 1362.60  5024.5 1366.69  5044.4 1367.51
  5049.6 1366.81  5055.5 1367.76  5090.1 1368.84  5179.5 1378.76  5220.9 1380.46
  5322.9 1386.83  5328.0 1387.93  5344.9 1388.34  5363.4 1390.07  5386.2 1390.57
#Mann=3,-1,0
  4783.4    0.12       0  4992.1    0.07       0  4996.1    0.12       0
Bank Sta=4992.1,4996.1
Exp/Cntr=0.3,0.1

Type RM Length L Ch R = 1,7406,406,406,406
BEGIN DESCRIPTION:
COLORADO 04 15.0
END DESCRIPTION:
XS GIS Cut Line= 3
      2863755.69     10294053.11      2864305.68     10293853.11
      2864617.90     10293730.38
#Sta/Elev= 30
  4414.6 1396.73  4449.3 1395.10  4551.7 1386.56  4629.4 1382.39  4775.7 1371.15
  4898.1 1358.00  4978.5 1357.15  4995.2 1354.49  4995.4 1353.99  4999.2 1354.49
  5002.5 1354.49  5009.3 1357.99  5021.3 1366.64  5032.1 1370.50  5039.1 1375.54
  5063.5 1383.98  5068.9 1384.05  5093.3 1393.34  5098.7 1393.30  5117.7 1397.99
  5123.1 1397.43  5147.5 1402.21  5177.3 1405.85  5182.7 1404.77  5201.7 1406.84
  5207.1 1406.06  5231.5 1409.75  5255.9 1410.88  5291.1 1409.55  5335.3 1413.11
#Mann=6,-1,0
  4414.6    0.05       0  4449.3    0.12       0  4551.7    0.05       0
  4629.4    0.12       0  4995.2    0.07       0  4999.2    0.12       0
Bank Sta=4995.2,4999.2
Exp/Cntr=0.3,0.1

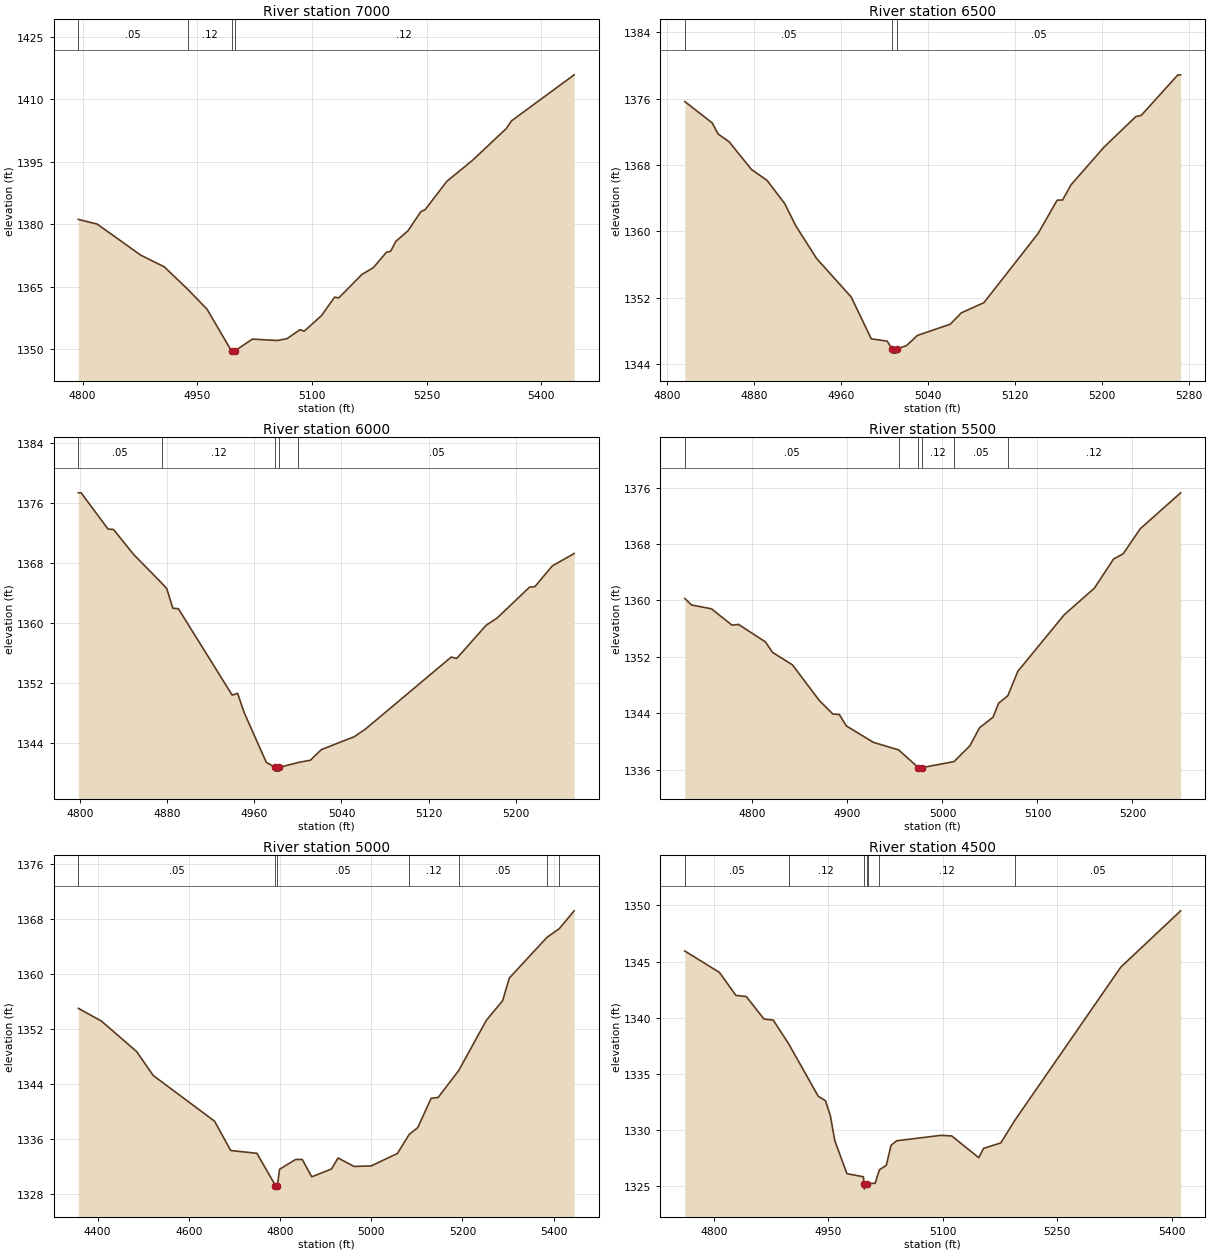
Type RM Length L Ch R = 1,7000,500,500,500
BEGIN DESCRIPTION:
COLORADO 04 14.0
END DESCRIPTION:
XS GIS Cut Line= 3
      2863955.70     10294153.12      2864156.70     10294195.88
      2864555.67     10294003.12
#Sta/Elev= 30
  4794.5 1381.22  4819.3 1380.07  4876.3 1372.61  4906.9 1369.84  4938.2 1364.34
  4962.9 1359.65  4994.9 1349.62  4995.2 1349.12  4998.9 1349.62  5022.2 1352.49
  5054.4 1352.15  5067.4 1352.58  5084.5 1354.75  5090.0 1354.39  5112.6 1358.13
  5129.7 1362.55  5135.2 1362.37  5165.5 1368.02  5180.4 1369.62  5197.5 1373.33
  5203.0 1373.56  5209.9 1375.95  5225.6 1378.45  5242.7 1383.09  5248.2 1383.55
  5276.5 1390.34  5309.8 1395.33  5354.3 1403.01  5361.2 1404.87  5443.1 1415.90
#Mann=4,-1,0
  4794.5    0.05       0  4938.2    0.12       0  4994.9    0.07       0
  4998.9    0.12       0
Bank Sta=4994.9,4998.9
Exp/Cntr=0.3,0.1

Type RM Length L Ch R = 1,6500,500,500,500
BEGIN DESCRIPTION:
COLORADO 04 13.0
END DESCRIPTION:
XS GIS Cut Line= 3
      2863905.66     10294653.11      2864085.54     10294689.88
      2864355.65     10294653.12
#Sta/Elev= 30
  4816.4 1375.64  4841.7 1373.06  4847.0 1371.74  4857.3 1370.78  4877.7 1367.46
  4892.1 1366.14  4908.3 1363.35  4918.5 1360.68  4937.5 1356.76  4969.5 1352.09
  4988.0 1347.05  5002.6 1346.78  5007.2 1345.83  5007.4 1345.33  5010.9 1345.33
  5011.2 1345.83  5020.3 1346.23  5030.4 1347.46  5060.7 1348.82  5070.8 1350.18
  5091.6 1351.41  5141.4 1359.73  5159.0 1363.76  5164.0 1363.78  5171.7 1365.60
  5202.0 1370.13  5231.4 1373.83  5236.4 1373.98  5270.1 1378.86  5272.6 1378.86
#Mann=3,-1,0
  4816.4    0.05       0  5007.2    0.05       0  5011.2    0.05       0
Bank Sta=5007.2,5011.2
Exp/Cntr=0.3,0.1

Type RM Length L Ch R = 1,6000,500,500,500
BEGIN DESCRIPTION:
COLORADO 04 12.0
END DESCRIPTION:
XS GIS Cut Line= 3
      2863905.67     10295153.11      2864104.37     10295187.77
      2864355.69     10295153.11
#Sta/Elev= 30
  4798.3 1377.30  4800.9 1377.30  4825.6 1372.47  4830.6 1372.42  4849.1 1369.09
  4874.9 1365.27  4879.5 1364.54  4885.1 1361.92  4890.2 1361.86  4939.6 1350.35
  4944.6 1350.58  4950.6 1348.03  4970.9 1341.40  4979.0 1340.72  4979.3 1340.22
  4982.8 1340.22  4983.0 1340.72  5000.5 1341.38  5011.4 1341.67  5021.5 1343.09
  5051.8 1344.81  5061.9 1345.81  5140.8 1355.42  5145.8 1355.23  5172.9 1359.66
  5183.0 1360.63  5212.7 1364.73  5217.7 1364.81  5233.5 1367.55  5253.7 1369.22
#Mann=5,-1,0
  4798.3    0.05       0  4874.9    0.12       0  4979.0    0.07       0
  4983.0    0.12       0  5000.5    0.05       0
Bank Sta=4979,4983
Exp/Cntr=0.3,0.1

Type RM Length L Ch R = 1,5500,500,500,500
BEGIN DESCRIPTION:
COLORADO 04 11.0
END DESCRIPTION:
XS GIS Cut Line= 3
      2863905.65     10295503.08      2864107.03     10295684.73
      2864355.73     10295653.11
#Sta/Elev= 30
  4728.8 1360.28  4735.9 1359.36  4756.9 1358.82  4778.5 1356.50  4785.3 1356.61
  4813.7 1354.13  4821.1 1352.65  4842.1 1350.88  4870.5 1345.81  4884.7 1343.91
  4891.4 1343.85  4898.9 1342.22  4927.3 1339.90  4954.0 1338.82  4974.6 1336.32
  4974.8 1335.82  4978.6 1336.32  5012.2 1337.17  5028.9 1339.41  5039.0 1341.96
  5053.3 1343.47  5059.1 1345.44  5068.8 1346.50  5079.3 1349.95  5128.2 1357.98
  5159.9 1361.74  5180.1 1365.87  5190.2 1366.61  5208.2 1370.16  5250.7 1375.25
#Mann=6,-1,0
  4728.8    0.05       0  4954.0    0.12       0  4974.6    0.07       0
  4978.6    0.12       0  5012.2    0.05       0  5068.8    0.12       0
Bank Sta=4974.6,4978.6
Exp/Cntr=0.3,0.1

Type RM Length L Ch R = 1,5000,500,500,500
BEGIN DESCRIPTION:
COLORADO 04 10.0
END DESCRIPTION:
XS GIS Cut Line= 3
      2863455.68     10296553.12      2863958.49     10296153.45
      2864355.72     10295953.09
#Sta/Elev= 30
  4357.7 1355.01  4408.2 1353.16  4485.4 1348.73  4521.9 1345.24  4656.5 1338.59
  4691.7 1334.33  4749.4 1333.92  4790.0 1329.21  4790.3 1328.71  4794.0 1329.21
  4799.0 1331.60  4834.3 1333.03  4848.7 1333.03  4869.5 1330.50  4912.8 1331.64
  4927.2 1333.24  4962.4 1332.01  5000.0 1332.09  5057.4 1333.90  5083.3 1336.68
  5102.0 1337.66  5131.3 1341.92  5146.6 1342.04  5191.8 1345.96  5252.5 1353.28
  5288.1 1356.12  5302.7 1359.41  5385.1 1365.32  5412.3 1366.60  5444.9 1369.19
#Mann=7,-1,0
  4357.7    0.05       0  4790.0    0.05       0  4794.0    0.05       0
  5083.3    0.12       0  5191.8    0.05       0  5385.1    0.12       0
  5412.3    0.05       0
Bank Sta=4790,4794
Exp/Cntr=0.3,0.1

Type RM Length L Ch R = 1,4500,500,500,500
BEGIN DESCRIPTION:
COLORADO 04 9.0
END DESCRIPTION:
XS GIS Cut Line= 3
      2863755.67     10296753.12      2863962.23     10296635.09
      2864205.70     10296303.09
#Sta/Elev= 30
  4762.1 1345.94  4807.5 1344.03  4829.1 1341.98  4842.7 1341.88  4865.8 1339.88
  4878.0 1339.78  4898.0 1337.69  4937.0 1332.99  4946.4 1332.60  4952.9 1331.23
  4958.6 1329.04  4974.5 1326.10  4996.1 1325.82  4996.9 1325.22  4997.2 1324.72
  5001.3 1325.22  5001.5 1325.22  5011.5 1325.24  5017.0 1326.44  5026.1 1326.84
  5032.3 1328.62  5039.7 1329.03  5097.2 1329.51  5111.8 1329.46  5147.3 1327.52
  5153.5 1328.35  5176.1 1328.84  5194.5 1330.85  5333.3 1344.50  5411.7 1349.52
#Mann=7,-1,0
  4762.1    0.05       0  4898.0    0.12       0  4996.9    0.07       0
  5001.3    0.12       0  5001.5    0.05       0  5017.0    0.12       0
  5194.5    0.05       0
Bank Sta=4996.9,5001.3
Exp/Cntr=0.3,0.1

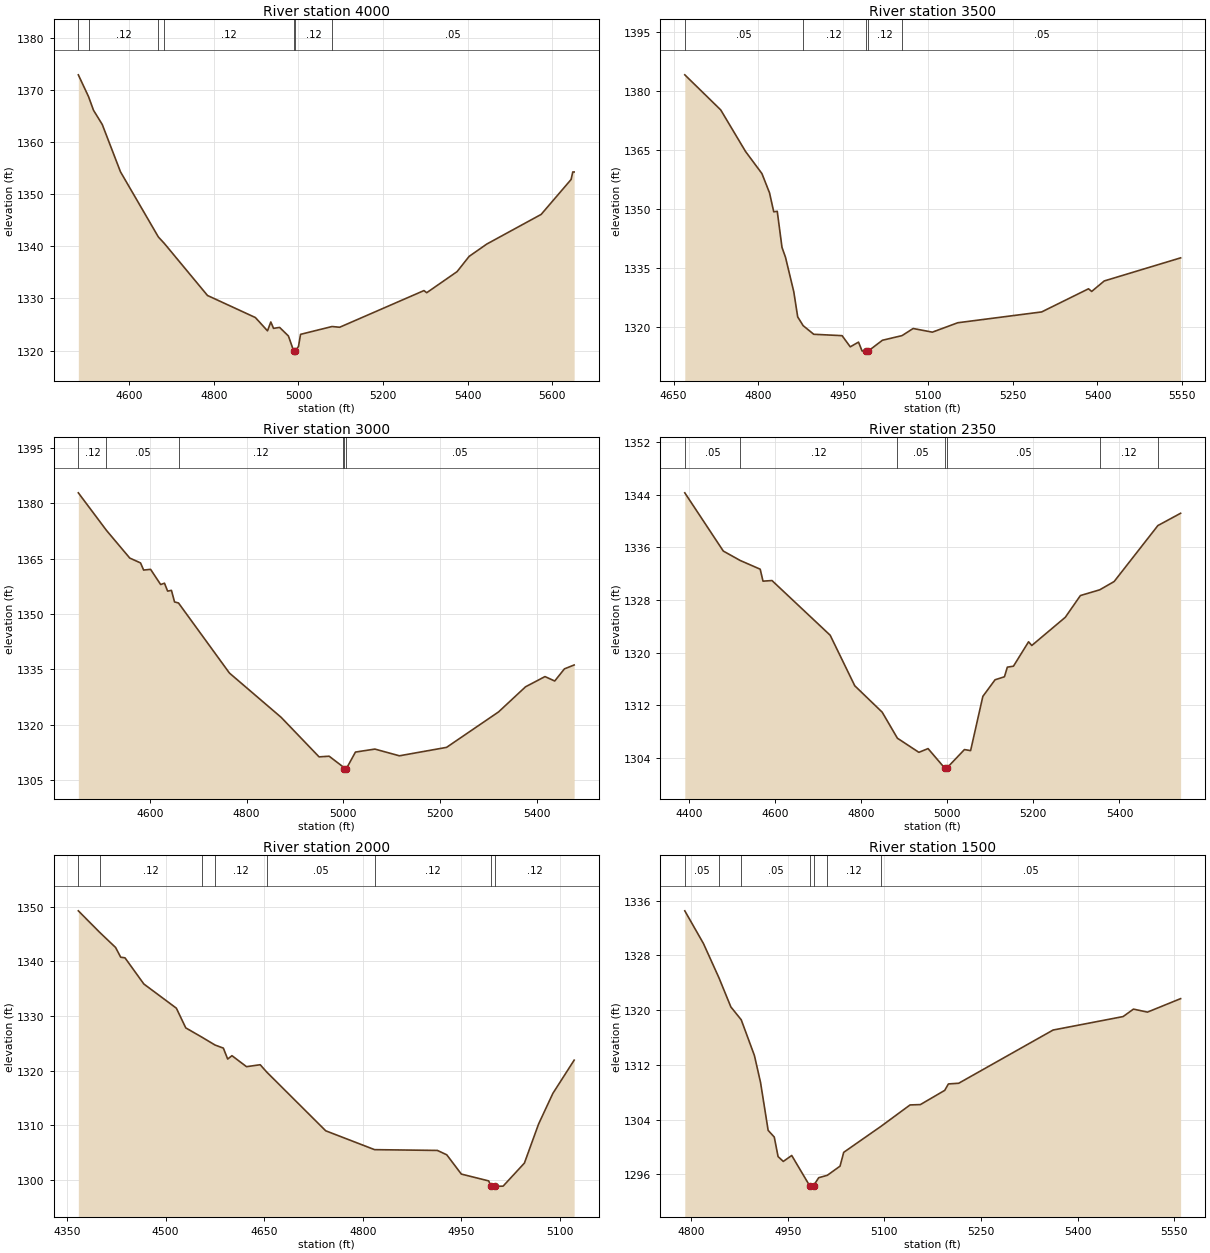
Type RM Length L Ch R = 1,4000,500,500,500
BEGIN DESCRIPTION:
COLORADO 04 8.0
END DESCRIPTION:
XS GIS Cut Line= 3
      2863955.67     10297403.13      2864289.51     10297004.18
      2864705.71     10296503.08
#Sta/Elev= 30
  4479.8 1372.86  4504.1 1368.65  4515.6 1366.08  4536.4 1363.33  4579.4 1354.27
  4668.9 1341.78  4683.0 1340.54  4785.0 1330.56  4898.2 1326.33  4926.8 1323.78
  4934.6 1325.48  4941.1 1324.26  4955.4 1324.44  4976.2 1322.80  4988.3 1320.01
  4988.6 1319.51  4992.8 1320.01  5000.0 1320.78  5004.9 1323.11  5079.3 1324.61
  5097.3 1324.47  5296.5 1331.50  5303.0 1331.09  5374.7 1335.13  5403.3 1338.06
  5445.0 1340.42  5573.4 1346.10  5644.2 1352.80  5648.1 1354.24  5651.4 1354.24
#Mann=7,-1,0
  4479.8    0.05       0  4504.1    0.12       0  4668.9    0.05       0
  4683.0    0.12       0  4988.3    0.07       0  4992.8    0.12       0
  5079.3    0.05       0
Bank Sta=4988.3,4992.8
Exp/Cntr=0.3,0.1

Type RM Length L Ch R = 1,3500,500,500,500
BEGIN DESCRIPTION:
COLORADO 04 7.0
END DESCRIPTION:
XS GIS Cut Line= 3
      2864305.67     10297703.13      2864503.50     10297438.63
      2864755.68     10296953.12
#Sta/Elev= 30
  4669.7 1384.20  4733.3 1375.28  4777.1 1364.74  4806.2 1359.10  4819.6 1354.22
  4827.1 1349.39  4833.3 1349.51  4841.7 1340.35  4847.9 1337.82  4862.5 1329.11
  4869.5 1322.68  4879.1 1320.46  4897.9 1318.26  4948.0 1317.91  4962.5 1315.07
  4977.1 1316.27  4983.4 1314.03  4989.5 1313.97  4989.8 1313.47  4994.0 1313.97
  5019.4 1316.74  5054.1 1317.92  5073.8 1319.73  5107.8 1318.80  5152.7 1321.19
  5301.2 1323.94  5384.1 1329.82  5389.7 1329.15  5411.9 1331.81  5547.1 1337.68
#Mann=5,-1,0
  4669.7    0.05       0  4879.1    0.12       0  4989.5    0.07       0
  4994.0    0.12       0  5054.1    0.05       0
Bank Sta=4989.5,4994
Exp/Cntr=0.3,0.1

Type RM Length L Ch R = 1,3000,650,650,650
BEGIN DESCRIPTION:
COLORADO 04 6.0
END DESCRIPTION:
XS GIS Cut Line= 3
      2864605.70     10297953.09      2864951.33     10297528.22
      2864905.68     10297053.11
#Sta/Elev= 30
  4452.3 1382.80  4510.4 1372.64  4558.6 1365.14  4580.9 1363.82  4587.3 1361.89
  4601.7 1362.08  4622.5 1357.97  4630.4 1358.33  4636.9 1356.19  4644.8 1356.39
  4651.2 1353.26  4659.4 1352.97  4764.7 1334.00  4871.7 1322.00  4950.0 1311.31
  4970.8 1311.49  4998.8 1308.69  5001.1 1307.95  5001.5 1307.45  5005.7 1307.95
  5025.2 1312.61  5065.4 1313.42  5116.0 1311.60  5213.5 1313.88  5321.0 1323.48
  5376.8 1330.28  5417.0 1333.05  5437.1 1331.85  5457.2 1335.14  5477.3 1336.19
#Mann=6,-1,0
  4452.3    0.12       0  4510.4    0.05       0  4659.4    0.12       0
  4998.8    0.05       0  5001.1    0.05       0  5005.7    0.05       0
Bank Sta=5001.1,5005.7
Exp/Cntr=0.3,0.1

Type RM Length L Ch R = 1,2350,350,350,350
BEGIN DESCRIPTION:
COLORADO 04 5.0
END DESCRIPTION:
XS GIS Cut Line= 3
      2865133.50     10297897.05      2865528.50     10297433.00
      2865888.33     10297027.68
#Sta/Elev= 30
  4390.6 1344.31  4480.0 1335.45  4519.4 1334.01  4565.7 1332.69  4572.2 1330.87
  4593.1 1330.96  4728.2 1322.64  4785.3 1314.95  4849.0 1310.93  4884.3 1306.97
  4934.2 1304.82  4955.5 1305.39  4993.7 1302.46  4994.2 1301.96  4999.6 1302.46
  5040.0 1305.24  5054.3 1305.08  5082.7 1313.33  5111.1 1315.86  5132.9 1316.32
  5139.6 1317.78  5153.8 1317.93  5188.9 1321.64  5196.4 1321.08  5274.2 1325.37
  5309.3 1328.68  5354.1 1329.55  5387.6 1330.81  5489.2 1339.33  5542.0 1341.20
#Mann=7,-1,0
  4390.6    0.05       0  4519.4    0.12       0  4884.3    0.05       0
  4993.7    0.05       0  4999.6    0.05       0  5354.1    0.12       0
  5489.2    0.05       0
Bank Sta=4993.7,4999.6
Exp/Cntr=0.3,0.1

Type RM Length L Ch R = 1,2000,500,500,500
BEGIN DESCRIPTION:
COLORADO 04 4.0
END DESCRIPTION:
XS GIS Cut Line= 3
      2865255.67     10298103.12      2865743.06     10297699.53
      2865855.67     10297653.12
#Sta/Elev= 30
  4367.2 1349.29  4399.8 1345.33  4423.9 1342.57  4431.7 1340.78  4438.2 1340.67
  4466.9 1335.87  4516.4 1331.43  4530.7 1327.82  4555.6 1326.09  4575.3 1324.67
  4587.9 1324.11  4594.5 1322.10  4601.0 1322.72  4623.2 1320.70  4644.0 1321.06
  4653.8 1319.73  4743.7 1308.94  4818.1 1305.48  4913.6 1305.34  4927.9 1304.54
  4950.1 1301.00  4991.7 1299.75  4995.5 1298.74  4996.0 1298.24  5001.4 1298.74
  5013.7 1298.79  5046.1 1303.02  5067.7 1310.19  5089.4 1315.80  5121.8 1321.90
#Mann=8,-1,0
  4367.2    0.05       0  4399.8    0.12       0  4555.6    0.05       0
  4575.3    0.12       0  4653.8    0.05       0  4818.1    0.12       0
  4995.5    0.07       0  5001.4    0.12       0
Bank Sta=4995.5,5001.4
Exp/Cntr=0.3,0.1

Type RM Length L Ch R = 1,1500,500,500,500
BEGIN DESCRIPTION:
COLORADO 04 3.0
END DESCRIPTION:
XS GIS Cut Line= 3
      2865605.67     10298303.12      2865784.17     10298192.68
      2866055.68     10297703.13
#Sta/Elev= 30
  4790.1 1334.51  4819.1 1329.72  4843.4 1324.66  4861.6 1320.46  4877.7 1318.58
  4898.2 1313.35  4907.7 1309.41  4919.5 1302.41  4929.0 1301.43  4934.9 1298.58
  4943.0 1297.87  4956.1 1298.74  4983.9 1294.32  4984.4 1293.82  4989.9 1294.32
  4998.0 1295.49  5011.3 1295.84  5031.1 1297.18  5036.8 1299.20  5094.8 1303.01
  5139.8 1306.13  5155.8 1306.18  5193.6 1308.26  5199.3 1309.20  5215.3 1309.30
  5361.8 1317.08  5470.5 1319.05  5486.6 1320.14  5508.3 1319.70  5559.8 1321.67
#Mann=7,-1,0
  4790.1    0.05       0  4843.4    0.12       0  4877.7    0.05       0
  4983.9    0.05       0  4989.9    0.05       0  5011.3    0.12       0
  5094.8    0.05       0
Bank Sta=4983.9,4989.9
Exp/Cntr=0.3,0.1

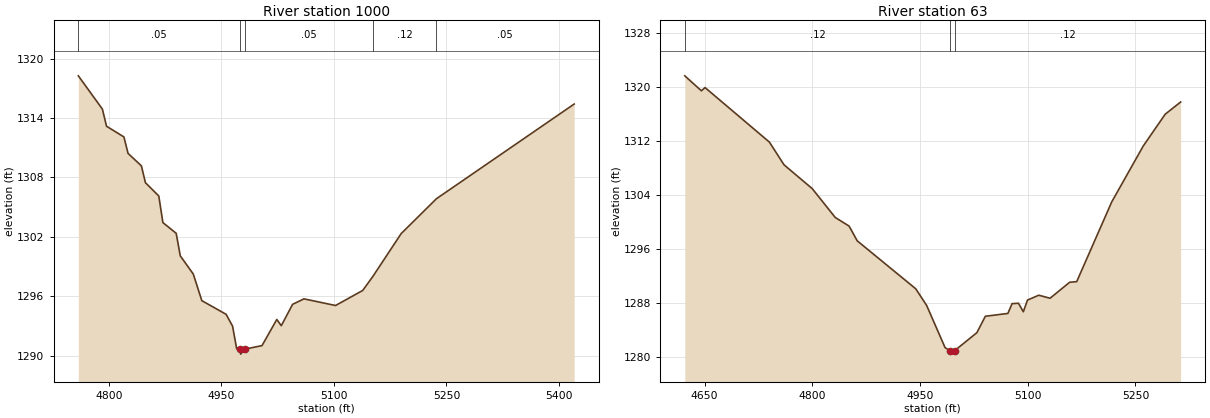
Type RM Length L Ch R = 1,1000,937,937,937
BEGIN DESCRIPTION:
COLORADO 04 2.0
END DESCRIPTION:
XS GIS Cut Line= 3
      2866005.66     10298503.12      2866225.70     10298405.05
      2866455.67     10298053.13
#Sta/Elev= 30
  4759.1 1318.26  4791.2 1314.90  4796.7 1313.17  4819.9 1312.09  4825.4 1310.43
  4843.2 1309.17  4848.6 1307.47  4866.4 1306.13  4871.9 1303.44  4889.6 1302.36
  4895.1 1300.08  4912.4 1298.25  4923.8 1295.56  4956.2 1294.18  4964.8 1292.99
  4970.3 1290.70  4975.1 1290.66  4975.6 1290.16  4981.1 1290.66  5004.1 1291.02
  5023.8 1293.66  5029.8 1293.03  5044.9 1295.19  5060.0 1295.74  5102.2 1295.07
  5138.4 1296.59  5151.8 1297.99  5189.7 1302.33  5236.7 1305.85  5420.4 1315.41
#Mann=5,-1,0
  4759.1    0.05       0  4975.1    0.05       0  4981.1    0.05       0
  5151.8    0.12       0  5236.7    0.05       0
Bank Sta=4975.1,4981.1
Exp/Cntr=0.3,0.1

Type RM Length L Ch R = 1,63,0,0,0
BEGIN DESCRIPTION:
COLORADO 04 1.0
END DESCRIPTION:
XS GIS Cut Line= 3
      2866130.08     10299023.23      2866500.50     10299096.00
      2866770.64     10298938.10
#Sta/Elev= 30
  4622.5 1321.72  4645.6 1319.50  4650.7 1319.98  4740.3 1311.90  4760.7 1308.53
  4799.9 1305.01  4832.0 1300.73  4851.3 1299.45  4862.6 1297.27  4944.1 1290.16
  4959.2 1287.71  4984.9 1281.45  4991.8 1280.98  4992.3 1280.48  4998.1 1280.98
  5029.2 1283.66  5041.0 1286.09  5072.4 1286.51  5078.2 1287.96  5087.1 1288.02
  5093.9 1286.76  5099.7 1288.49  5115.4 1289.21  5131.1 1288.76  5158.4 1291.13
  5168.2 1291.22  5217.0 1303.04  5260.8 1311.31  5291.4 1316.03  5312.9 1317.84
#Mann=3,-1,0
  4622.5    0.12       0  4991.8    0.07       0  4998.1    0.12       0
Bank Sta=4991.8,4998.1
Exp/Cntr=0.3,0.1

Chan Stop Cuts=-1