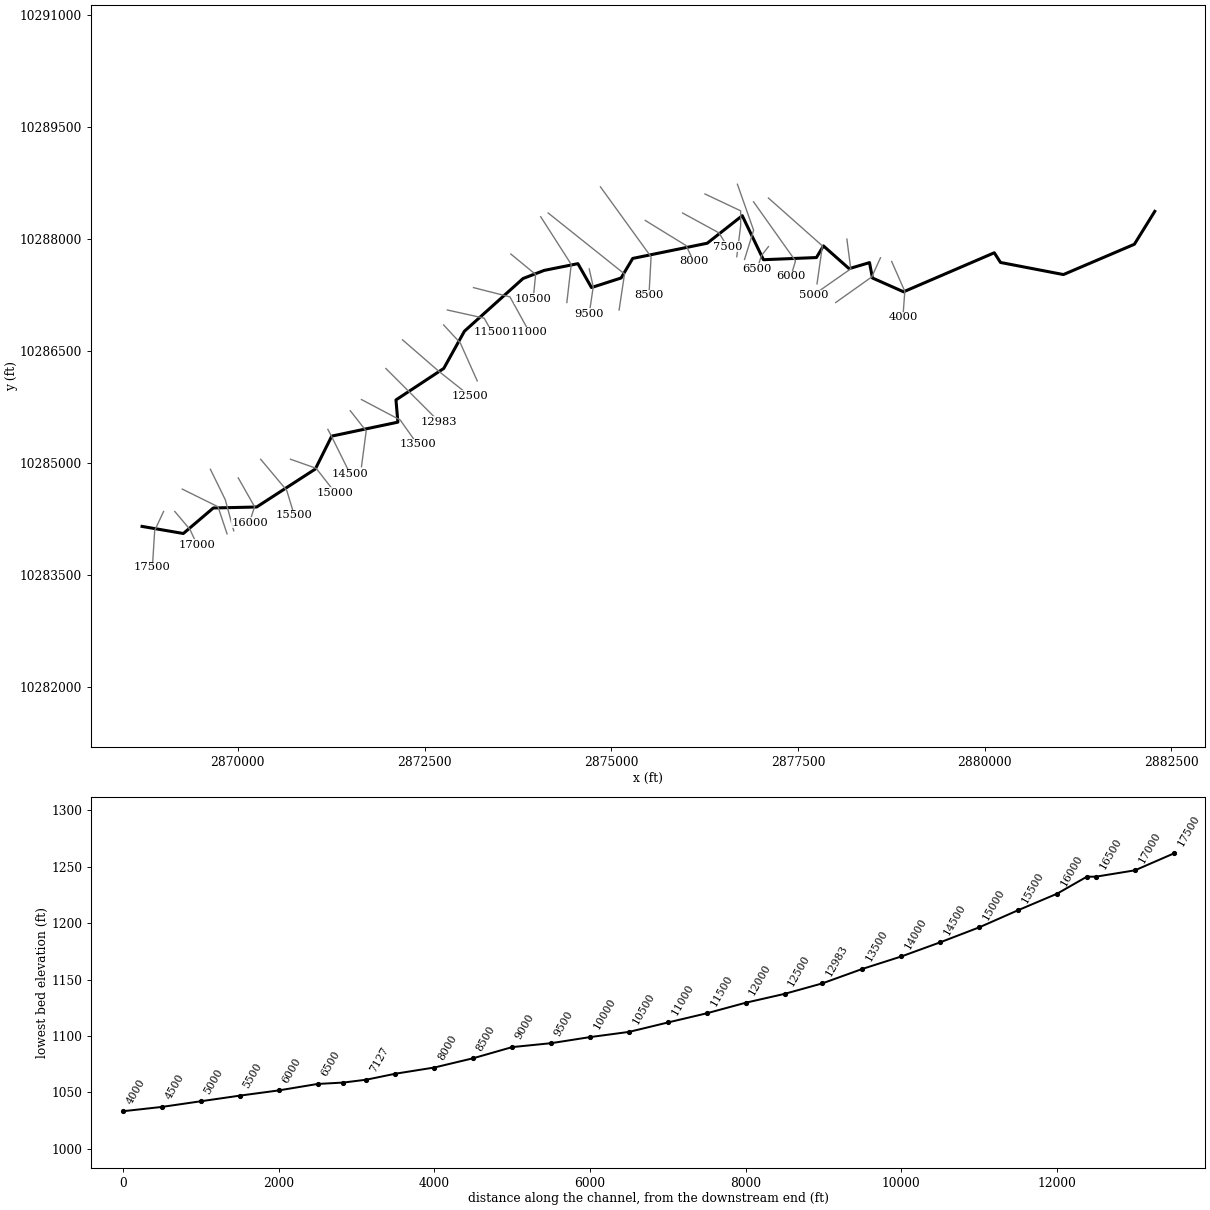
--- COLORADO 06.prj (project) ---

Proj Title=COLORADO 06 Base Level Engineering
Current Plan=p01
Default Exp/Contr=0.3,0.1
English Units
Geom File=g01
Flow File=f01
Plan File=p01
BEGIN DESCRIPTION:
COLORADO 06
END DESCRIPTION:

--- COLORADO 06.p01 (plan) ---

Plan Title=Multiple Run
Short Identifier=Multiple
Geom File=g01
Flow File=f01
Subcritical Flow
K Sum by GR= 0
Std Step Tol= 0.01
Critical Tol= 0.01
Num of Std Step Trials= 20
Max Error Tol= 0.3
Flow Tol Ratio= 0.001
Split Flow NTrial= 30
Split Flow Tol= 0.02
Split Flow Ratio= 0.02
Log Output Level= 0
Friction Slope Method= 1
Unsteady Friction Slope Method= 2
Unsteady Bridges Friction Slope Method= 1
Parabolic Critical Depth
Global Vel Dist=  1 , 1 , 1
Global Log Level= 0
CheckData=True
Encroach Param= -1, 0, 0, 0
BEGIN DESCRIPTION:
Multiple Run
END DESCRIPTION:

--- COLORADO 06.f01 (steady flow) ---

Flow Title=Multiple
Number of Profiles=7
Profile Names=10-year,25-year,50-year,1pct_min,100-year,1pct_plu,500-year
River Rch & RM= COLORADO 06,Reach-1,17500
     442     716    1302    1020    1803    3185    2580
River Rch & RM= COLORADO 06,Reach-1,10500
     846    1442    2439    1719    3431    6849    4880
Boundary for River Rch & Prof#=COLORADO 06,Reach-1,1
Up Type=0
Dn Type=3
Dn Slope=0.005
Boundary for River Rch & Prof#=COLORADO 06,Reach-1,2
Up Type=0
Dn Type=3
Dn Slope=0.005
Boundary for River Rch & Prof#=COLORADO 06,Reach-1,3
Up Type=0
Dn Type=3
Dn Slope=0.005
Boundary for River Rch & Prof#=COLORADO 06,Reach-1,4
Up Type=0
Dn Type=3
Dn Slope=0.005
Boundary for River Rch & Prof#=COLORADO 06,Reach-1,5
Up Type=0
Dn Type=3
Dn Slope=0.005
Boundary for River Rch & Prof#=COLORADO 06,Reach-1,6
Up Type=0
Dn Type=3
Dn Slope=0.005
Boundary for River Rch & Prof#=COLORADO 06,Reach-1,7
Up Type=0
Dn Type=3
Dn Slope=0.005

--- COLORADO 06.g01 (geometry) ---

Geom Title=Existing Conditions

River Reach=COLORADO 06,Reach-1
Reach XY= 30
      2868717.50     10284153.00      2869270.25     10284058.00
      2869671.75     10284400.00      2870252.25     10284413.00
      2871037.75     10284922.00      2871257.50     10285363.00
      2872143.25     10285550.00      2872117.75     10285848.00
      2872757.50     10286270.00      2873034.25     10286769.00
      2873819.25     10287475.00      2874103.00     10287584.00
      2874553.75     10287674.00      2874735.75     10287354.00
      2875132.50     10287482.00      2875287.75     10287744.00
      2876285.75     10287948.00      2876754.50     10288317.00
      2877038.25     10287727.00      2877748.00     10287756.00
      2877841.75     10287912.00      2878185.50     10287607.00
      2878458.75     10287688.00      2878498.00     10287482.00
      2878914.50     10287297.00      2880129.50     10287820.00
      2880213.00     10287690.00      2881055.50     10287528.00
      2882005.50     10287934.00      2882278.75     10288375.00

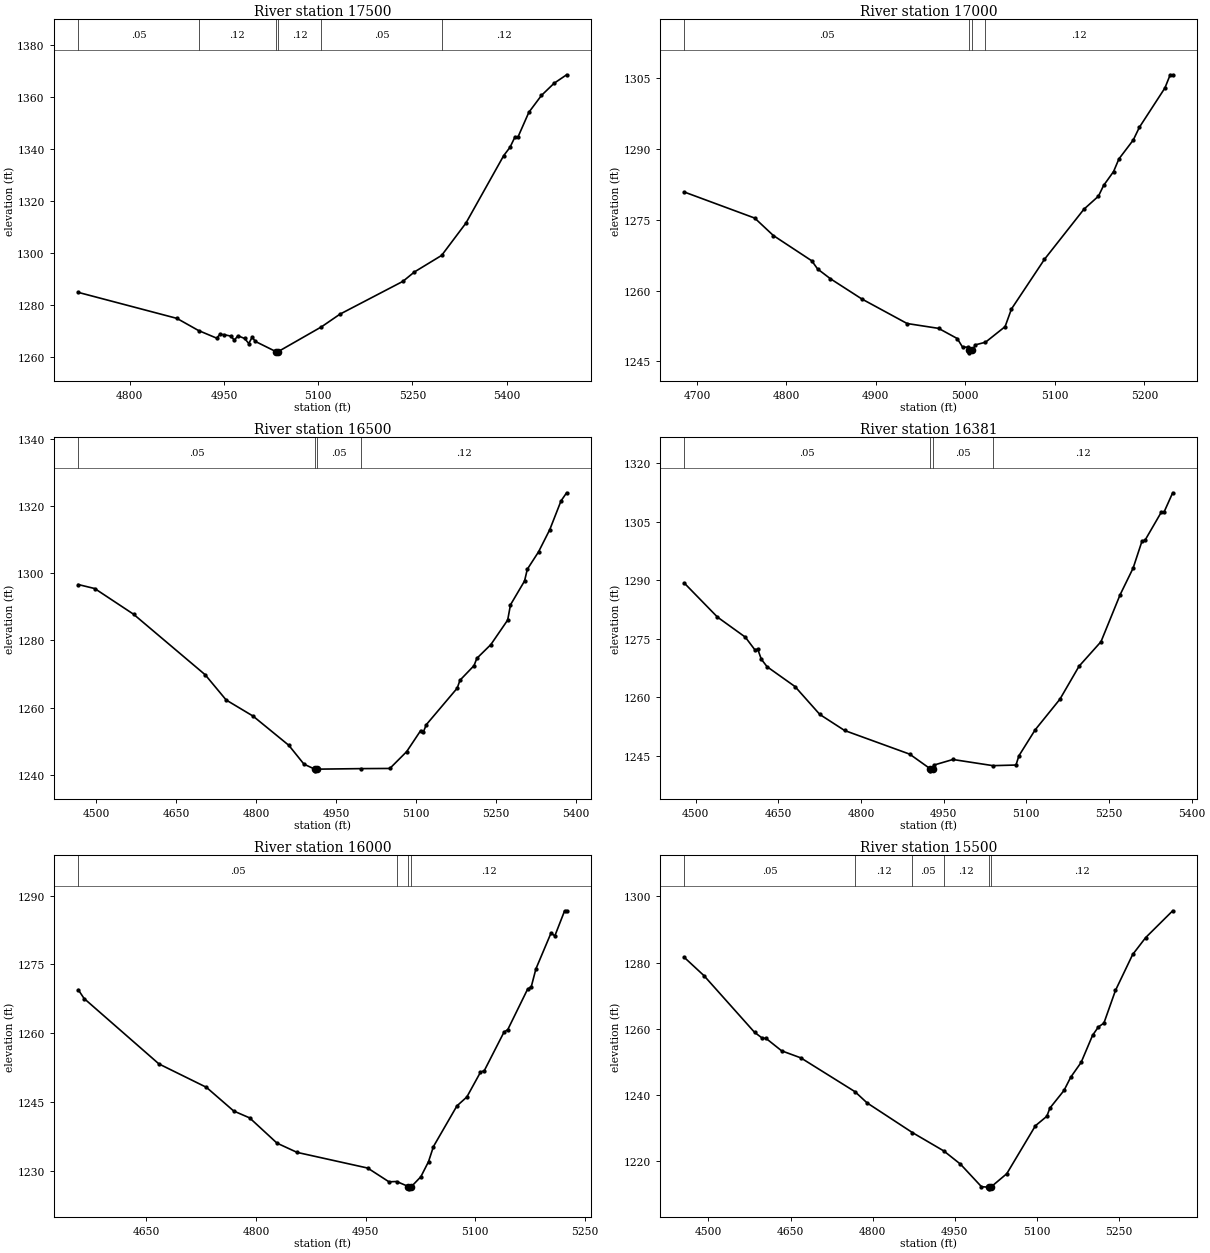
Type RM Length L Ch R = 1,17500,500,500,500
BEGIN DESCRIPTION:
COLORADO 06 35.0
END DESCRIPTION:
XS GIS Cut Line= 3
      2869005.71     10284353.16      2868886.77     10284097.68
      2868855.69     10283603.16
#Sta/Elev= 30
  4718.2 1285.04  4875.2 1275.04  4909.6 1270.37  4938.3 1267.46  4943.9 1268.90
  4949.9 1268.79  4960.9 1268.23  4966.7 1266.68  4972.3 1268.35  4983.0 1267.31
  4989.6 1265.38  4995.1 1267.86  4999.8 1266.21  5032.6 1262.29  5032.9 1261.79
  5036.6 1262.29  5105.2 1271.77  5134.8 1276.67  5235.0 1289.29  5253.3 1292.90
  5296.6 1299.26  5335.2 1311.67  5395.4 1337.64  5405.4 1340.83  5413.1 1344.70
  5418.1 1344.79  5435.4 1354.29  5455.5 1360.79  5475.5 1365.44  5495.5 1368.72
#Mann=6,-1,0
  4718.2    0.05       0  4909.6    0.12       0  5032.6    0.07       0
  5036.6    0.12       0  5105.2    0.05       0  5296.6    0.12       0
Bank Sta=5032.6,5036.6
Exp/Cntr=0.3,0.1

Type RM Length L Ch R = 1,17000,500,500,500
BEGIN DESCRIPTION:
COLORADO 06 34.0
END DESCRIPTION:
XS GIS Cut Line= 3
      2869155.66     10284353.14      2869358.41     10284113.38
      2869455.70     10283903.09
#Sta/Elev= 30
  4686.0 1280.90  4764.6 1275.38  4785.5 1271.67  4828.4 1266.31  4834.9 1264.58
  4849.2 1262.51  4884.3 1258.22  4934.9 1253.01  4970.1 1251.98  4990.9 1249.83
  4996.9 1248.00  5002.7 1248.00  5003.6 1247.29  5003.9 1246.79  5007.6 1247.29
  5011.3 1248.49  5022.5 1249.04  5044.4 1252.35  5051.5 1256.09  5088.4 1266.63
  5132.5 1277.26  5148.7 1280.02  5154.5 1282.30  5165.6 1285.24  5171.6 1287.93
  5187.6 1291.93  5194.5 1294.65  5223.0 1302.98  5228.9 1305.78  5231.7 1305.78
#Mann=4,-1,0
  4686.0    0.05       0  5003.6    0.05       0  5007.6    0.05       0
  5022.5    0.12       0
Bank Sta=5003.6,5007.6
Exp/Cntr=0.3,0.1

Type RM Length L Ch R = 1,16500,119,119,119
BEGIN DESCRIPTION:
COLORADO 06 33.0
END DESCRIPTION:
XS GIS Cut Line= 3
      2869255.66     10284653.12      2869734.58     10284416.48
      2869855.68     10284053.13
#Sta/Elev= 30
  4465.8 1296.62  4496.7 1295.43  4569.6 1287.79  4704.2 1269.77  4743.6 1262.26
  4794.0 1257.48  4861.3 1248.77  4889.7 1243.17  4910.0 1241.68  4910.2 1241.18
  4914.0 1241.68  4997.6 1241.84  5051.0 1241.89  5082.6 1246.90  5108.9 1253.16
  5114.2 1252.84  5119.5 1254.92  5177.5 1265.78  5182.7 1268.14  5209.1 1272.49
  5214.4 1274.66  5240.7 1278.75  5272.3 1286.05  5277.6 1290.59  5304.0 1297.68
  5309.2 1301.18  5330.3 1306.35  5351.4 1312.97  5372.5 1321.51  5383.0 1323.93
#Mann=4,-1,0
  4465.8    0.05       0  4910.0    0.07       0  4914.0    0.05       0
  4997.6    0.12       0
Bank Sta=4910,4914
Exp/Cntr=0.3,0.1

Type RM Length L Ch R = 1,16381,381,381,381
BEGIN DESCRIPTION:
Mapping XS d0e06ee9
END DESCRIPTION:
XS GIS Cut Line= 3
      2869632.54     10284918.50      2869832.20     10284510.50
      2869945.05     10284093.85
#Sta/Elev= 30
  4479.6 1289.25  4539.7 1280.54  4590.2 1275.40  4607.2 1272.21  4612.8 1272.26
  4619.2 1269.74  4629.7 1267.81  4680.3 1262.73  4725.3 1255.57  4770.3 1251.45
  4888.4 1245.38  4925.9 1241.60  4926.1 1241.10  4929.9 1241.60  4932.1 1242.57
  4966.8 1244.01  5039.4 1242.43  5081.2 1242.59  5086.5 1244.96  5115.9 1251.60
  5160.9 1259.48  5195.6 1267.94  5235.4 1274.23  5270.1 1286.28  5293.7 1293.11
  5309.9 1300.08  5315.1 1300.21  5344.6 1307.41  5349.8 1307.49  5365.5 1312.44
#Mann=4,-1,0
  4479.6    0.05       0  4925.9    0.05       0  4929.9    0.05       0
  5039.4    0.12       0
Bank Sta=4925.9,4929.9
Exp/Cntr=0.3,0.1

Type RM Length L Ch R = 1,16000,500,500,500
BEGIN DESCRIPTION:
COLORADO 06 32.0
END DESCRIPTION:
XS GIS Cut Line= 3
      2870005.68     10284803.12      2870224.16     10284417.40
      2870155.67     10284203.07
#Sta/Elev= 30
  4556.7 1269.48  4564.7 1267.57  4667.1 1253.31  4732.0 1248.22  4769.5 1243.04
  4791.2 1241.55  4828.7 1236.04  4856.1 1234.03  4952.8 1230.61  4981.9 1227.61
  4992.4 1227.68  5008.6 1226.58  5008.8 1226.08  5012.6 1226.58  5025.5 1228.71
  5036.0 1232.00  5042.8 1235.31  5074.9 1244.16  5088.5 1246.11  5107.1 1251.50
  5112.4 1251.86  5139.3 1260.24  5144.5 1260.80  5171.5 1269.57  5176.7 1270.18
  5183.0 1274.04  5203.6 1281.82  5208.9 1281.23  5222.3 1286.70  5225.0 1286.70
#Mann=4,-1,0
  4556.7    0.05       0  4992.4    0.12       0  5008.6    0.07       0
  5012.6    0.12       0
Bank Sta=5008.6,5012.6
Exp/Cntr=0.3,0.1

Type RM Length L Ch R = 1,15500,500,500,500
BEGIN DESCRIPTION:
COLORADO 06 31.0
END DESCRIPTION:
XS GIS Cut Line= 3
      2870305.70     10285053.09      2870654.77     10284635.99
      2870755.67     10284303.15
#Sta/Elev= 30
  4456.1 1281.53  4491.9 1276.03  4584.2 1258.87  4598.5 1257.08  4605.1 1257.04
  4633.7 1253.26  4668.8 1251.12  4767.6 1240.89  4789.8 1237.48  4872.5 1228.50
  4929.9 1222.93  4960.3 1218.93  4998.6 1212.11  5011.5 1211.96  5011.7 1211.46
  5015.5 1211.96  5044.8 1216.04  5097.1 1230.56  5118.0 1233.44  5123.5 1235.90
  5149.3 1241.25  5161.6 1245.27  5180.6 1249.75  5201.5 1257.96  5212.0 1260.47
  5222.2 1261.66  5243.3 1271.55  5274.7 1282.43  5298.5 1287.56  5347.8 1295.67
#Mann=6,-1,0
  4456.1    0.05       0  4767.6    0.12       0  4872.5    0.05       0
  4929.9    0.12       0  5011.5    0.07       0  5015.5    0.12       0
Bank Sta=5011.5,5015.5
Exp/Cntr=0.3,0.1

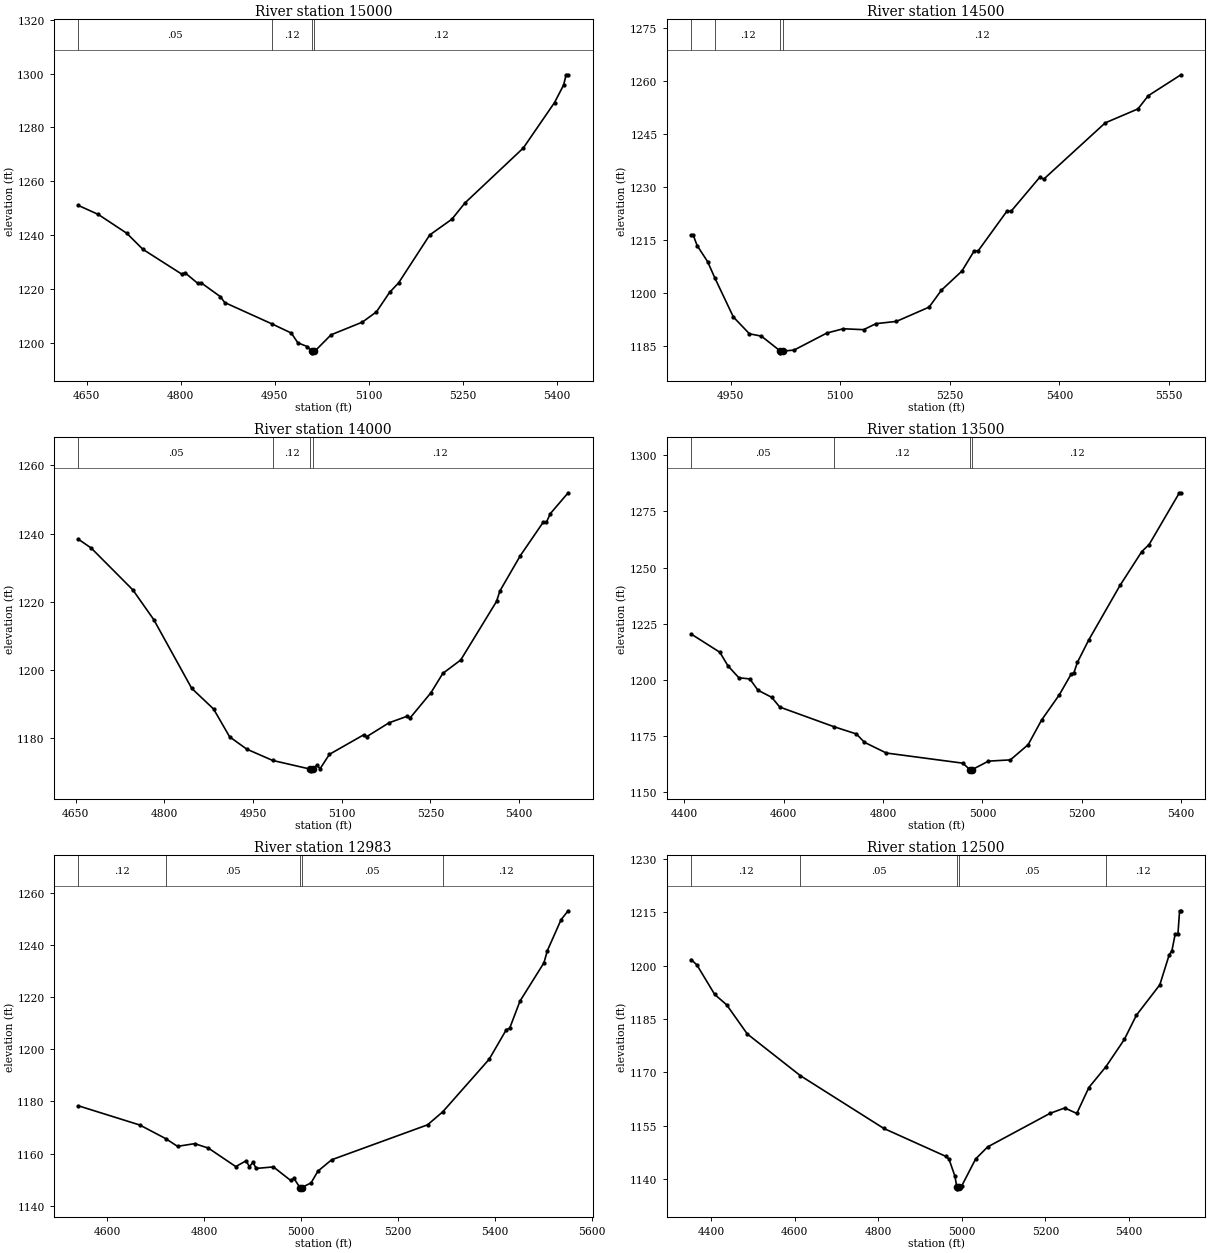
Type RM Length L Ch R = 1,15000,500,500,500
BEGIN DESCRIPTION:
COLORADO 06 30.0
END DESCRIPTION:
XS GIS Cut Line= 3
      2870705.67     10285053.12      2871048.16     10284931.93
      2871305.71     10284603.08
#Sta/Elev= 30
  4636.7 1251.04  4668.5 1247.69  4714.0 1240.68  4739.6 1234.73  4801.4 1225.54
  4806.7 1226.03  4827.0 1222.10  4832.3 1222.32  4863.2 1217.13  4870.1 1214.95
  4945.8 1206.97  4976.2 1203.62  4986.8 1199.96  5002.0 1198.58  5009.2 1196.76
  5009.5 1196.26  5013.2 1196.76  5039.7 1202.96  5089.5 1207.67  5112.0 1211.48
  5132.9 1218.71  5147.3 1222.24  5197.0 1240.07  5232.3 1245.92  5253.1 1251.95
  5346.2 1272.38  5396.0 1289.28  5410.4 1295.75  5414.5 1299.59  5417.7 1299.59
#Mann=4,-1,0
  4636.7    0.05       0  4945.8    0.12       0  5009.2    0.07       0
  5013.2    0.12       0
Bank Sta=5009.2,5013.2
Exp/Cntr=0.3,0.1

Type RM Length L Ch R = 1,14500,500,500,500
BEGIN DESCRIPTION:
COLORADO 06 29.0
END DESCRIPTION:
XS GIS Cut Line= 3
      2871205.67     10285453.13      2871254.38     10285360.79
      2871505.70     10284853.09
#Sta/Elev= 30
  4895.6 1216.43  4898.4 1216.43  4903.8 1213.43  4918.2 1208.86  4928.1 1204.24
  4953.5 1193.16  4975.5 1188.41  4991.9 1187.74  5017.8 1183.51  5018.0 1183.01
  5021.8 1183.51  5036.6 1183.79  5081.5 1188.62  5103.9 1189.83  5131.9 1189.58
  5148.8 1191.28  5176.8 1191.92  5221.6 1195.97  5238.5 1200.78  5266.5 1206.18
  5283.3 1211.90  5288.9 1211.95  5328.2 1223.18  5333.8 1223.12  5373.0 1232.74
  5378.6 1232.24  5462.8 1248.19  5507.6 1252.14  5521.8 1255.89  5566.5 1261.82
#Mann=4,-1,0
  4895.6    0.05       0  4928.1    0.12       0  5017.8    0.07       0
  5021.8    0.12       0
Bank Sta=5017.8,5021.8
Exp/Cntr=0.3,0.1

Type RM Length L Ch R = 1,14000,500,500,500
BEGIN DESCRIPTION:
COLORADO 06 28.0
END DESCRIPTION:
XS GIS Cut Line= 3
      2871505.69     10285703.11      2871718.88     10285431.61
      2871655.68     10284953.06
#Sta/Elev= 30
  4654.8 1238.36  4676.5 1235.77  4747.0 1223.48  4782.3 1214.77  4846.4 1194.64
  4883.4 1188.57  4910.6 1180.40  4939.5 1176.81  4983.2 1173.50  5046.9 1170.95
  5047.2 1170.45  5050.9 1170.95  5058.3 1172.14  5063.3 1171.04  5079.2 1175.29
  5136.8 1180.98  5141.9 1180.44  5180.0 1184.54  5210.3 1186.43  5215.3 1185.91
  5250.7 1193.33  5270.8 1199.01  5301.1 1202.94  5361.6 1220.11  5367.4 1223.21
  5402.0 1233.58  5440.9 1243.43  5445.9 1243.30  5452.4 1245.82  5482.7 1251.97
#Mann=4,-1,0
  4654.8    0.05       0  4983.2    0.12       0  5046.9    0.07       0
  5050.9    0.12       0
Bank Sta=5046.9,5050.9
Exp/Cntr=0.3,0.1

Type RM Length L Ch R = 1,13500,517,517,517
BEGIN DESCRIPTION:
COLORADO 06 27.0
END DESCRIPTION:
XS GIS Cut Line= 3
      2871655.72     10285853.09      2872174.36     10285579.04
      2872405.70     10285253.09
#Sta/Elev= 30
  4413.4 1220.40  4471.2 1212.27  4487.6 1206.21  4509.6 1200.89  4531.6 1200.38
  4548.0 1195.34  4575.6 1192.20  4592.0 1187.83  4700.8 1179.10  4746.1 1175.86
  4762.4 1172.14  4806.5 1167.36  4960.5 1162.84  4974.9 1159.92  4975.1 1159.42
  4978.9 1159.92  5012.2 1163.75  5056.3 1164.30  5092.1 1171.09  5119.2 1182.08
  5154.8 1193.29  5178.3 1202.37  5184.4 1203.23  5191.2 1207.74  5213.9 1217.67
  5277.0 1242.03  5320.9 1257.13  5335.7 1260.28  5396.6 1283.33  5399.7 1283.33
#Mann=4,-1,0
  4413.4    0.05       0  4700.8    0.12       0  4974.9    0.07       0
  4978.9    0.12       0
Bank Sta=4974.9,4978.9
Exp/Cntr=0.3,0.1

Type RM Length L Ch R = 1,12983,483,483,483
BEGIN DESCRIPTION:
Mapping XS 8258b31e
END DESCRIPTION:
XS GIS Cut Line= 2
      2871982.21     10286269.28      2872697.38     10285554.11
#Sta/Elev= 30
  4540.4 1178.35  4667.4 1170.98  4720.8 1165.77  4745.2 1162.82  4780.6 1163.85
  4808.8 1162.16  4865.4 1155.07  4886.6 1157.25  4893.7 1155.05  4900.8 1156.66
  4907.8 1154.36  4943.2 1154.94  4978.6 1149.78  4985.6 1150.57  4997.8 1147.04
  4998.0 1146.54  5001.8 1147.04  5021.0 1148.83  5035.1 1153.32  5063.4 1157.67
  5261.4 1171.05  5292.9 1176.05  5388.7 1196.18  5424.0 1207.47  5431.1 1208.08
  5452.3 1218.44  5501.8 1233.12  5508.9 1237.80  5537.2 1249.65  5551.8 1253.05
#Mann=5,-1,0
  4540.4    0.12       0  4720.8    0.05       0  4997.8    0.05       0
  5001.8    0.05       0  5292.9    0.12       0
Bank Sta=4997.8,5001.8
Exp/Cntr=0.3,0.1

Type RM Length L Ch R = 1,12500,500,500,500
BEGIN DESCRIPTION:
COLORADO 06 25.0
END DESCRIPTION:
XS GIS Cut Line= 3
      2872205.68     10286653.12      2872694.99     10286228.60
      2873105.66     10285903.13
#Sta/Elev= 30
  4352.2 1201.68  4366.0 1200.16  4408.7 1191.86  4437.2 1188.96  4486.6 1180.77
  4613.8 1169.04  4813.3 1154.23  4961.4 1146.40  4969.0 1145.66  4983.3 1140.83
  4987.9 1137.77  4988.1 1137.27  4991.9 1137.77  5000.0 1138.18  5032.9 1145.67
  5061.7 1149.05  5210.8 1158.47  5246.0 1159.98  5274.9 1158.45  5303.7 1165.72
  5344.6 1171.58  5388.6 1179.23  5417.5 1186.04  5473.5 1194.58  5496.0 1203.01
  5502.4 1204.14  5510.4 1208.90  5516.8 1208.72  5520.8 1215.37  5524.0 1215.37
#Mann=5,-1,0
  4352.2    0.12       0  4613.8    0.05       0  4987.9    0.05       0
  4991.9    0.05       0  5344.6    0.12       0
Bank Sta=4987.9,4991.9
Exp/Cntr=0.3,0.1

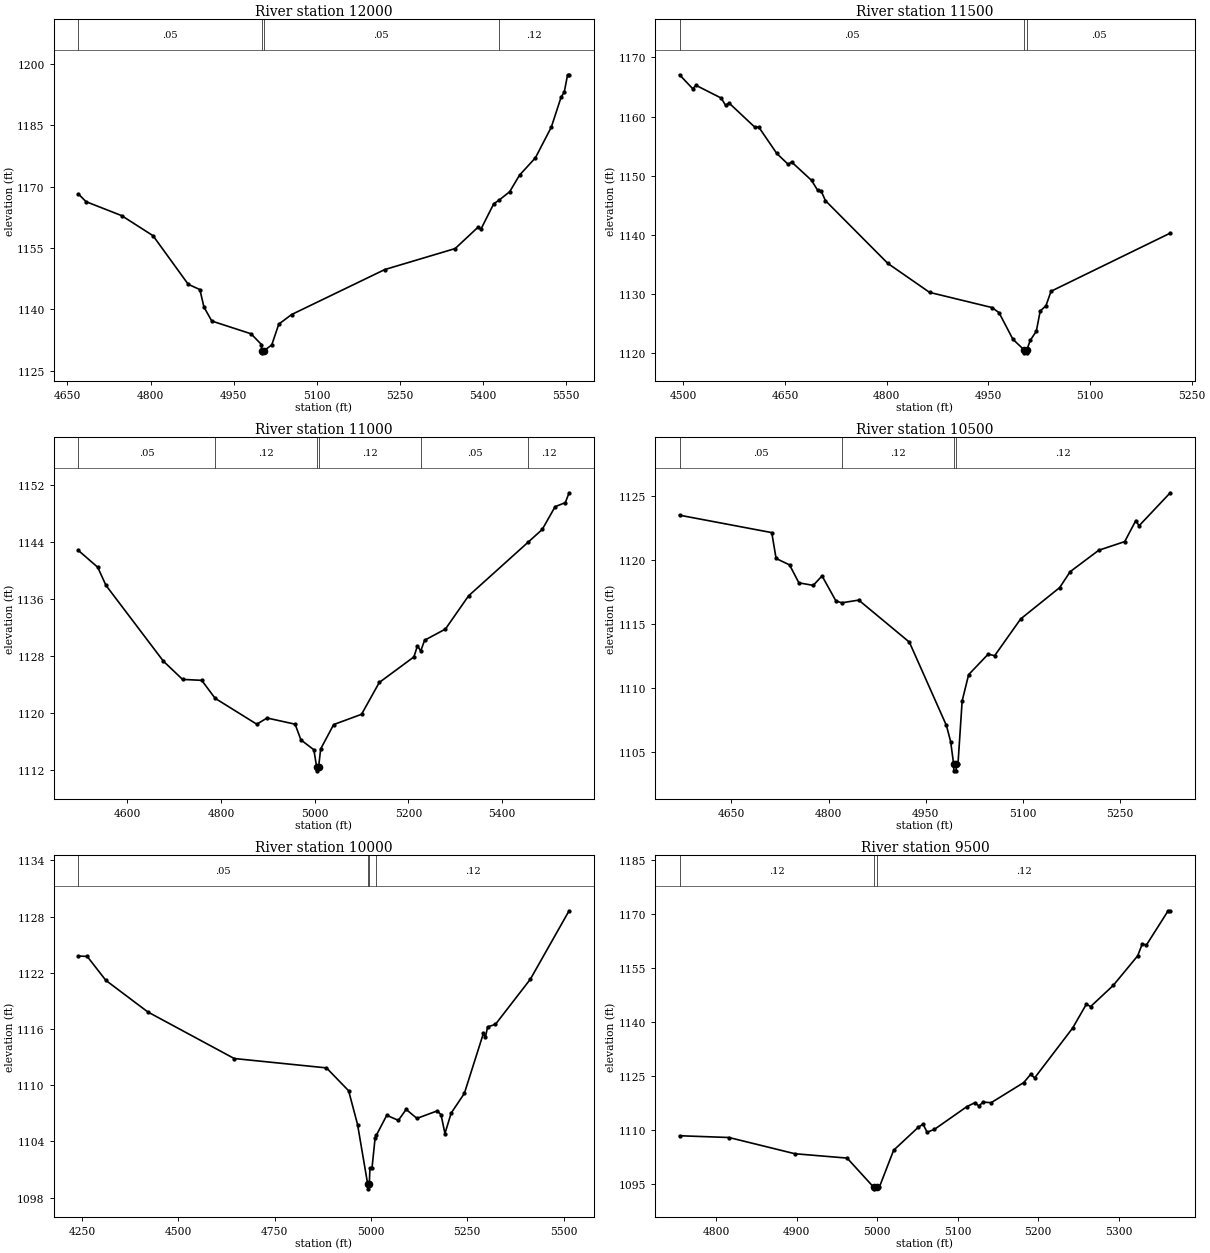
Type RM Length L Ch R = 1,12000,500,500,500
BEGIN DESCRIPTION:
COLORADO 06 24.0
END DESCRIPTION:
XS GIS Cut Line= 3
      2872755.69     10286853.11      2872979.50     10286610.20
      2873205.67     10286103.15
#Sta/Elev= 30
  4669.7 1168.22  4683.6 1166.34  4747.7 1162.94  4804.4 1158.03  4867.9 1146.16
  4888.9 1144.87  4896.3 1140.59  4910.4 1137.18  4981.3 1134.06  5000.0 1131.44
  5000.6 1129.91  5000.8 1129.41  5004.6 1129.91  5018.7 1131.36  5031.3 1136.42
  5054.5 1138.77  5222.6 1149.76  5349.6 1154.89  5390.6 1160.07  5396.1 1159.63
  5419.3 1165.85  5428.3 1166.66  5448.0 1168.78  5465.8 1172.83  5494.4 1177.06
  5523.1 1184.55  5540.9 1191.93  5546.4 1193.08  5552.5 1197.35  5555.2 1197.35
#Mann=4,-1,0
  4669.7    0.05       0  5000.6    0.05       0  5004.6    0.05       0
  5428.3    0.12       0
Bank Sta=5000.6,5004.6
Exp/Cntr=0.3,0.1

Type RM Length L Ch R = 1,11500,500,500,500
BEGIN DESCRIPTION:
COLORADO 06 23.0
END DESCRIPTION:
XS GIS Cut Line= 3
      2872805.65     10287053.12      2873299.05     10286943.62
      2873405.67     10286753.13
#Sta/Elev= 30
  4494.6 1167.06  4513.9 1164.72  4519.0 1165.27  4556.1 1163.12  4562.5 1161.89
  4567.7 1162.28  4606.1 1158.15  4611.2 1158.26  4638.0 1153.76  4654.8 1151.92
  4659.9 1152.32  4689.3 1149.21  4698.4 1147.51  4703.5 1147.40  4709.7 1145.79
  4801.9 1135.16  4863.4 1130.27  4955.6 1127.70  4965.8 1126.84  4986.3 1122.34
  5002.8 1120.55  5003.1 1120.05  5006.6 1120.05  5006.8 1120.55  5012.0 1122.20
  5020.8 1123.70  5026.5 1127.11  5035.0 1128.01  5042.5 1130.46  5218.3 1140.29
#Mann=3,-1,0
  4494.6    0.05       0  5002.8    0.05       0  5006.8    0.05       0
Bank Sta=5002.8,5006.8
Exp/Cntr=0.3,0.1

Type RM Length L Ch R = 1,11000,500,500,500
BEGIN DESCRIPTION:
COLORADO 06 22.0
END DESCRIPTION:
XS GIS Cut Line= 3
      2873155.69     10287353.11      2873644.15     10287228.53
      2873905.68     10286753.11
#Sta/Elev= 30
  4495.9 1142.84  4537.2 1140.48  4554.6 1137.95  4677.2 1127.29  4718.1 1124.73
  4759.0 1124.60  4787.5 1122.08  4876.4 1118.44  4898.4 1119.31  4958.2 1118.44
  4970.6 1116.23  4998.2 1114.85  5004.2 1112.39  5004.4 1111.89  5008.2 1112.39
  5012.7 1114.96  5040.4 1118.39  5099.9 1119.83  5137.7 1124.30  5211.6 1127.89
  5219.2 1129.46  5226.1 1128.71  5234.4 1130.23  5278.8 1131.80  5328.1 1136.46
  5455.9 1144.04  5485.3 1145.79  5512.8 1148.99  5534.6 1149.56  5542.6 1150.94
#Mann=6,-1,0
  4495.9    0.05       0  4787.5    0.12       0  5004.2    0.07       0
  5008.2    0.12       0  5226.1    0.05       0  5455.9    0.12       0
Bank Sta=5004.2,5008.2
Exp/Cntr=0.3,0.1

Type RM Length L Ch R = 1,10500,500,500,500
BEGIN DESCRIPTION:
COLORADO 06 21.0
END DESCRIPTION:
XS GIS Cut Line= 3
      2873655.69     10287803.10      2873987.73     10287529.57
      2873955.69     10287203.13
#Sta/Elev= 30
  4569.8 1123.50  4712.3 1122.14  4719.0 1120.12  4739.8 1119.62  4754.2 1118.22
  4776.4 1118.02  4790.0 1118.76  4811.5 1116.80  4820.6 1116.66  4846.7 1116.87
  4924.9 1113.59  4982.2 1107.08  4988.7 1105.82  4993.4 1104.04  4993.6 1103.54
  4997.2 1103.54  4997.5 1104.04  5000.0 1104.04  5006.5 1109.00  5016.5 1111.05
  5046.7 1112.65  5056.7 1112.53  5096.9 1115.40  5157.2 1117.85  5173.4 1119.09
  5217.5 1120.76  5257.7 1121.44  5274.8 1123.08  5279.8 1122.67  5328.0 1125.25
#Mann=4,-1,0
  4569.8    0.05       0  4820.6    0.12       0  4993.4    0.07       0
  4997.5    0.12       0
Bank Sta=4993.4,4997.5
Exp/Cntr=0.3,0.1

Type RM Length L Ch R = 1,10000,500,500,500
BEGIN DESCRIPTION:
COLORADO 06 20.0
END DESCRIPTION:
XS GIS Cut Line= 3
      2874055.66     10288303.15      2874464.72     10287663.93
      2874405.69     10287153.13
#Sta/Elev= 30
  4241.1 1123.79  4264.0 1123.75  4312.4 1121.19  4421.3 1117.82  4645.4 1112.85
  4884.7 1111.85  4942.2 1109.41  4965.4 1105.80  4991.7 1099.44  4992.0 1098.94
  4995.9 1099.44  4997.5 1101.17  5002.9 1101.17  5010.9 1104.37  5014.0 1104.65
  5041.1 1106.79  5071.3 1106.25  5091.4 1107.42  5119.4 1106.46  5172.0 1107.26
  5182.0 1106.85  5192.1 1104.84  5208.3 1107.03  5242.4 1109.12  5292.1 1115.56
  5297.1 1115.11  5302.8 1116.23  5323.0 1116.49  5413.6 1121.31  5514.2 1128.62
#Mann=4,-1,0
  4241.1    0.05       0  4991.7    0.03       0  4995.9    0.05       0
  5014.0    0.12       0
Bank Sta=4991.7,4995.9
Exp/Cntr=0.3,0.1

Type RM Length L Ch R = 1,9500,500,500,500
BEGIN DESCRIPTION:
COLORADO 06 19.0
END DESCRIPTION:
XS GIS Cut Line= 3
      2874705.68     10287603.11      2874759.22     10287363.21
      2874705.68     10287003.07
#Sta/Elev= 30
  4754.2 1108.32  4815.7 1107.83  4897.6 1103.31  4962.5 1102.10  4995.3 1094.04
  4995.6 1093.54  4999.6 1094.04  5002.6 1094.04  5020.3 1104.28  5050.7 1110.63
  5056.9 1111.55  5061.9 1109.30  5070.9 1110.08  5111.3 1116.42  5121.2 1117.51
  5126.3 1116.62  5131.5 1117.68  5141.6 1117.53  5182.1 1123.14  5190.6 1125.41
  5195.6 1124.43  5242.7 1138.27  5260.0 1145.00  5265.0 1144.25  5293.3 1150.18
  5323.6 1158.40  5329.4 1161.76  5334.4 1161.38  5361.5 1170.95  5364.1 1170.95
#Mann=3,-1,0
  4754.2    0.12       0  4995.3    0.07       0  4999.6    0.12       0
Bank Sta=4995.3,4999.6
Exp/Cntr=0.3,0.1

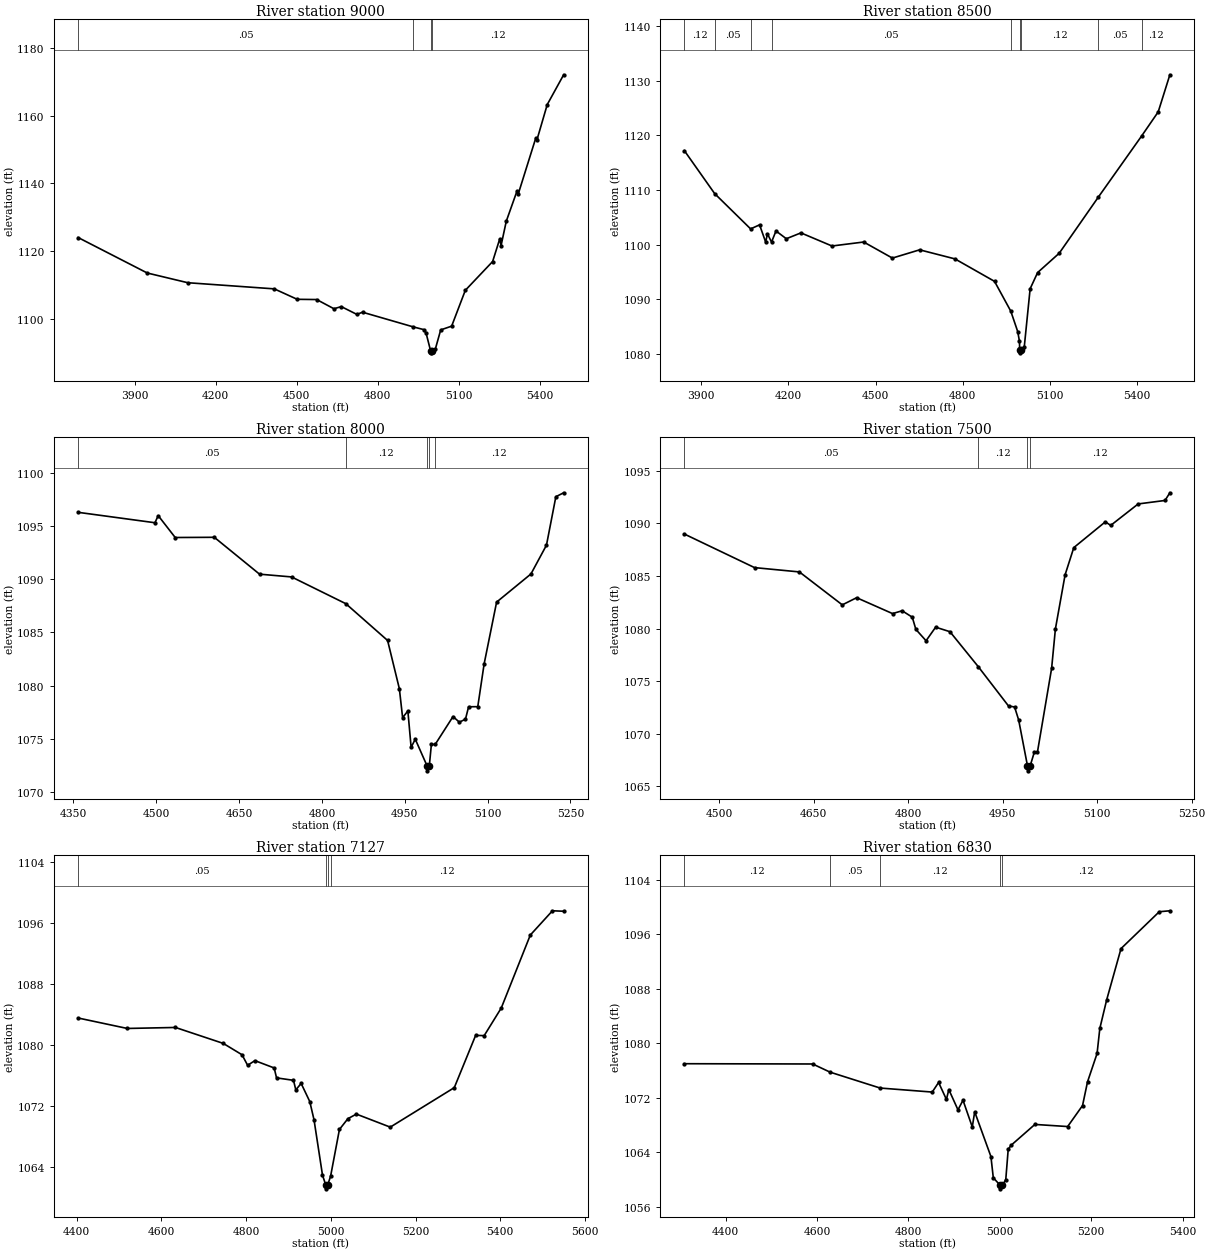
Type RM Length L Ch R = 1,9000,500,500,500
BEGIN DESCRIPTION:
COLORADO 06 18.0
END DESCRIPTION:
XS GIS Cut Line= 3
      2874155.68     10288353.11      2875178.22     10287536.19
      2875105.68     10287053.10
#Sta/Elev= 30
  3691.2 1124.06  3947.2 1113.60  4097.1 1110.74  4417.3 1108.93  4502.1 1105.85
  4574.2 1105.78  4638.2 1103.07  4665.4 1103.70  4723.1 1101.40  4743.9 1102.05
  4932.2 1097.71  4971.2 1096.91  4979.2 1095.91  4996.3 1090.57  4996.6 1090.07
  5000.6 1090.57  5013.2 1091.09  5033.4 1096.83  5073.9 1097.94  5124.5 1108.50
  5225.6 1116.99  5251.8 1123.62  5256.9 1121.70  5276.1 1128.86  5315.8 1137.76
  5320.9 1137.02  5384.9 1153.28  5390.0 1152.95  5427.8 1163.26  5488.5 1172.04
#Mann=4,-1,0
  3691.2    0.05       0  4932.2    0.12       0  4996.3    0.07       0
  5000.6    0.12       0
Bank Sta=4996.3,5000.6
Exp/Cntr=0.3,0.1

Type RM Length L Ch R = 1,8500,500,500,500
BEGIN DESCRIPTION:
COLORADO 06 17.0
END DESCRIPTION:
XS GIS Cut Line= 3
      2874855.66     10288703.15      2875533.90     10287764.93
      2875505.68     10287253.11
#Sta/Elev= 30
  3842.3 1117.21  3946.7 1109.34  4070.3 1102.89  4101.1 1103.63  4122.0 1100.48
  4128.2 1101.99  4142.2 1100.48  4157.6 1102.51  4193.1 1101.09  4243.4 1102.16
  4350.2 1099.76  4459.3 1100.49  4558.0 1097.55  4651.8 1099.06  4773.3 1097.40
  4909.4 1093.29  4965.3 1087.84  4989.1 1084.11  4995.3 1082.29  4995.8 1080.71
  4996.1 1080.21  5000.2 1080.71  5011.8 1081.34  5031.9 1091.94  5057.7 1094.90
  5132.0 1098.44  5266.7 1108.72  5415.2 1119.87  5472.5 1124.30  5512.6 1131.09
#Mann=9,-1,0
  3842.3    0.12       0  3946.7    0.05       0  4070.3    0.12       0
  4142.2    0.05       0  4965.3    0.12       0  4995.8    0.07       0
  5000.2    0.12       0  5266.7    0.05       0  5415.2    0.12       0
Bank Sta=4995.8,5000.2
Exp/Cntr=0.3,0.1

Type RM Length L Ch R = 1,8000,500,500,500
BEGIN DESCRIPTION:
COLORADO 06 16.0
END DESCRIPTION:
XS GIS Cut Line= 3
      2875455.65     10288253.13      2876002.07     10287917.06
      2876105.68     10287703.13
#Sta/Elev= 30
  4358.5 1096.30  4497.6 1095.32  4503.5 1095.99  4534.3 1093.93  4605.1 1093.95
  4687.0 1090.48  4745.0 1090.22  4843.3 1087.70  4918.9 1084.24  4940.2 1079.70
  4946.1 1076.97  4955.6 1077.61  4961.5 1074.18  4969.0 1074.95  4990.1 1072.47
  4990.4 1071.97  4994.5 1072.47  4998.2 1074.46  5005.0 1074.45  5037.4 1077.08
  5048.8 1076.55  5059.9 1076.83  5065.6 1078.00  5082.2 1078.01  5093.7 1082.03
  5116.3 1087.85  5178.5 1090.50  5206.6 1093.21  5223.6 1097.77  5237.7 1098.14
#Mann=5,-1,0
  4358.5    0.05       0  4843.3    0.12       0  4990.1    0.03       0
  4994.5    0.12       0  5005.0    0.12       0
Bank Sta=4990.1,4994.5
Exp/Cntr=0.3,0.1

Type RM Length L Ch R = 1,7500,373,373,373
BEGIN DESCRIPTION:
COLORADO 06 15.0
END DESCRIPTION:
XS GIS Cut Line= 3
      2875955.72     10288353.09      2876443.02     10288086.61
      2876555.67     10287903.13
#Sta/Elev= 30
  4444.6 1088.98  4556.0 1085.79  4627.2 1085.38  4695.3 1082.25  4718.1 1082.93
  4775.1 1081.42  4790.3 1081.69  4806.4 1081.08  4812.1 1079.92  4828.3 1078.84
  4843.5 1080.13  4866.2 1079.70  4911.0 1076.39  4959.2 1072.64  4968.8 1072.55
  4975.3 1071.31  4989.2 1066.98  4989.5 1066.48  4993.7 1066.98  5000.0 1068.23
  5005.0 1068.23  5027.6 1076.22  5033.6 1079.96  5049.0 1085.11  5062.8 1087.69
  5112.9 1090.14  5121.4 1089.80  5165.0 1091.84  5207.6 1092.17  5215.3 1092.90
#Mann=4,-1,0
  4444.6    0.05       0  4911.0    0.12       0  4989.2    0.07       0
  4993.7    0.12       0
Bank Sta=4989.2,4993.7
Exp/Cntr=0.3,0.1

Type RM Length L Ch R = 1,7127,297,297,297
BEGIN DESCRIPTION:
Mapping XS 8bc8f8fa
END DESCRIPTION:
XS GIS Cut Line= 4
      2876255.85     10288607.71      2876733.24     10288382.03
      2876733.24     10288182.38      2876681.31     10287766.91
#Sta/Elev= 30
  4403.3 1083.58  4519.3 1082.21  4633.1 1082.34  4746.0 1080.25  4790.3 1078.76
  4803.5 1077.38  4820.7 1077.99  4866.2 1077.03  4871.8 1075.73  4911.8 1075.41
  4917.3 1074.16  4929.9 1075.00  4950.3 1072.62  4960.3 1070.23  4980.3 1062.98
  4988.0 1061.68  4988.3 1061.18  4992.5 1061.68  4999.4 1062.83  5020.3 1068.97
  5040.3 1070.38  5060.3 1070.98  5140.3 1069.27  5291.5 1074.45  5341.9 1081.30
  5362.1 1081.27  5402.4 1084.89  5471.0 1094.46  5523.3 1097.64  5549.7 1097.58
#Mann=4,-1,0
  4403.3    0.05       0  4988.0    0.07       0  4992.5    0.05       0
  4999.4    0.12       0
Bank Sta=4988,4992.5
Exp/Cntr=0.3,0.1

Type RM Length L Ch R = 1,6830,330,330,330
BEGIN DESCRIPTION:
Mapping XS 5e3bacdd
END DESCRIPTION:
XS GIS Cut Line= 3
      2876689.83     10288737.96      2876906.86     10288121.61
      2876785.34     10287731.02
#Sta/Elev= 30
  4309.6 1076.99  4590.4 1076.95  4628.6 1075.75  4738.0 1073.42  4852.1 1072.83
  4866.0 1074.24  4883.1 1071.75  4888.4 1073.19  4908.4 1070.22  4919.4 1071.63
  4939.7 1067.71  4945.0 1069.93  4980.5 1063.37  4985.7 1060.25  5001.1 1059.13
  5001.4 1058.63  5005.6 1059.13  5013.0 1059.98  5018.3 1064.41  5024.3 1065.00
  5076.7 1068.08  5148.4 1067.77  5181.0 1070.85  5191.9 1074.33  5212.8 1078.49
  5218.8 1082.16  5233.8 1086.36  5265.2 1093.88  5348.9 1099.29  5372.1 1099.43
#Mann=5,-1,0
  4309.6    0.12       0  4628.6    0.05       0  4738.0    0.12       0
  5001.1    0.07       0  5005.6    0.12       0
Bank Sta=5001.1,5005.6
Exp/Cntr=0.3,0.1

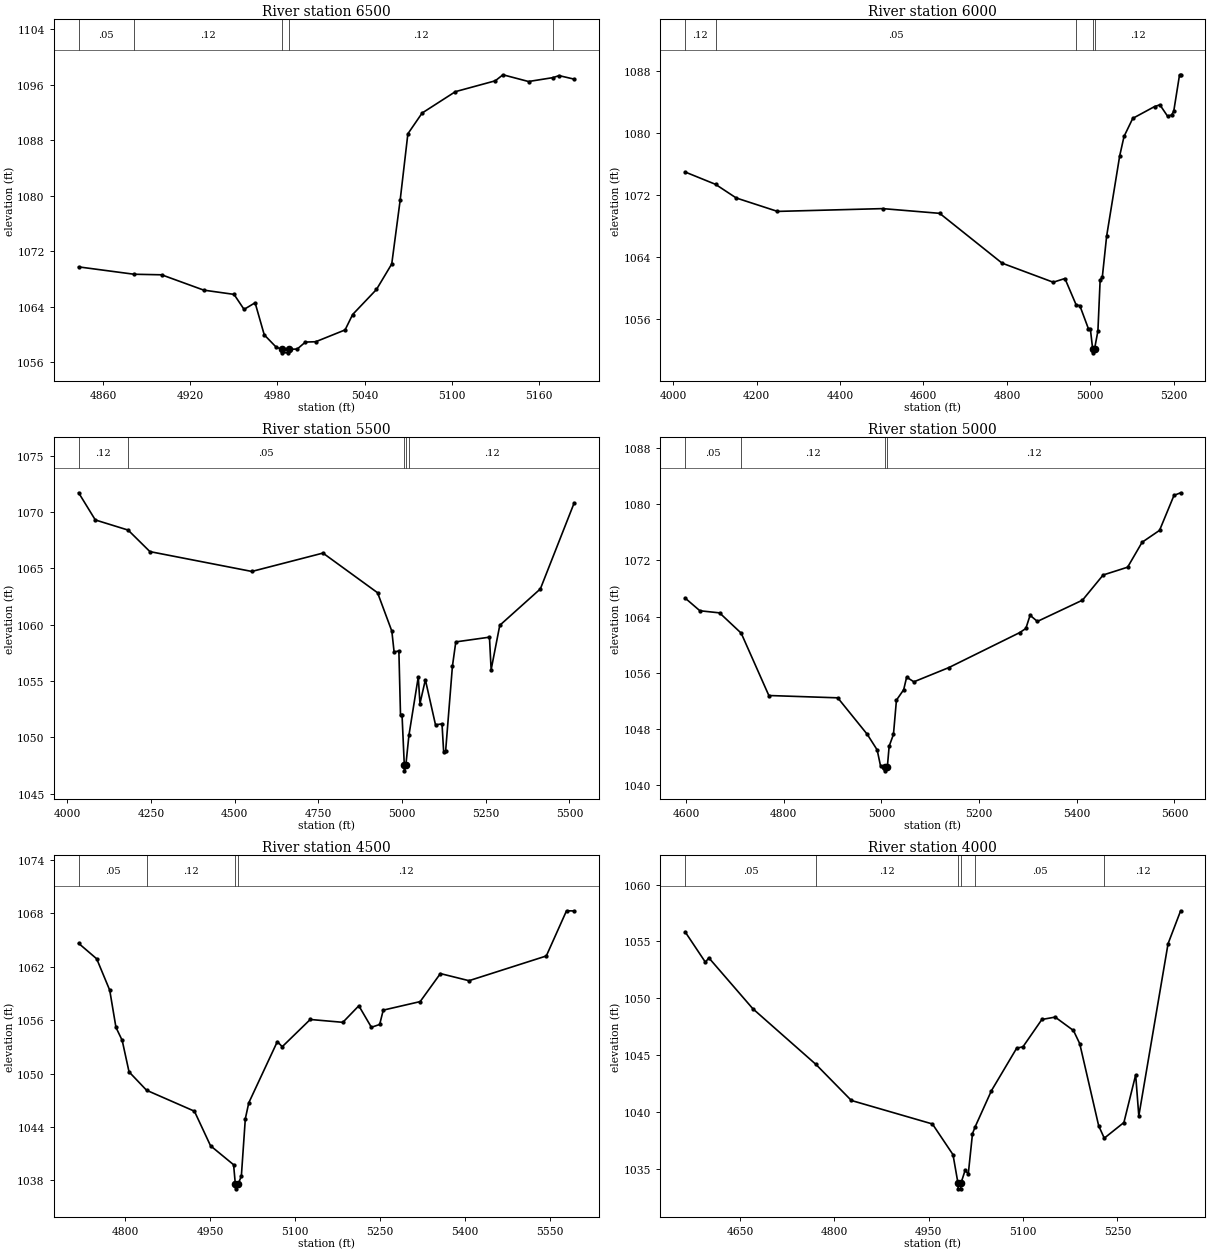
Type RM Length L Ch R = 1,6500,500,500,500
BEGIN DESCRIPTION:
COLORADO 06 13.0
END DESCRIPTION:
XS GIS Cut Line= 3
      2877105.71     10287903.14      2877009.84     10287779.20
      2876955.69     10287603.13
#Sta/Elev= 30
  4843.3 1069.77  4881.4 1068.71  4900.4 1068.63  4929.4 1066.42  4950.2 1065.81
  4957.1 1063.65  4964.7 1064.60  4971.0 1059.98  4979.2 1058.21  4983.2 1057.89
  4983.5 1057.39  4987.4 1057.39  4987.7 1057.89  4993.7 1057.94  4999.3 1058.94
  5006.4 1058.99  5026.6 1060.69  5031.8 1062.91  5048.2 1066.52  5058.7 1070.19
  5064.5 1079.39  5069.8 1088.94  5079.6 1091.93  5102.5 1095.01  5129.9 1096.57
  5135.2 1097.44  5152.8 1096.47  5169.6 1097.03  5173.8 1097.32  5184.2 1096.81
#Mann=5,-1,0
  4843.3    0.05       0  4881.4    0.12       0  4983.2    0.07       0
  4987.7    0.12       0  5169.6    0.05       0
Bank Sta=4983.2,4987.7
Exp/Cntr=0.3,0.1

Type RM Length L Ch R = 1,6000,500,500,500
BEGIN DESCRIPTION:
COLORADO 06 12.0
END DESCRIPTION:
XS GIS Cut Line= 3
      2876905.69     10288503.10      2877467.42     10287710.59
      2877405.68     10287503.08
#Sta/Elev= 30
  4028.6 1074.97  4101.5 1073.38  4151.2 1071.62  4250.1 1069.89  4502.3 1070.25
  4638.9 1069.64  4788.5 1063.22  4911.1 1060.76  4939.1 1061.24  4966.2 1057.82
  4974.8 1057.75  4995.4 1054.77  5000.0 1054.77  5005.6 1052.16  5005.9 1051.66
  5010.1 1052.16  5018.2 1054.48  5023.5 1061.01  5028.8 1061.45  5039.1 1066.70
  5070.4 1077.05  5080.8 1079.55  5101.7 1081.88  5153.9 1083.40  5166.7 1083.63
  5185.2 1082.16  5194.7 1082.32  5199.9 1082.78  5213.9 1087.50  5216.5 1087.50
#Mann=5,-1,0
  4028.6    0.12       0  4101.5    0.05       0  4966.2    0.12       0
  5005.6    0.07       0  5010.1    0.12       0
Bank Sta=5005.6,5010.1
Exp/Cntr=0.3,0.1

Type RM Length L Ch R = 1,5500,500,500,500
BEGIN DESCRIPTION:
COLORADO 06 11.0
END DESCRIPTION:
XS GIS Cut Line= 3
      2877105.65     10288553.14      2877828.08     10287912.00
      2877755.69     10287403.12
#Sta/Elev= 30
  4034.1 1071.70  4083.9 1069.29  4181.9 1068.39  4247.0 1066.48  4551.4 1064.72
  4763.8 1066.35  4926.9 1062.83  4969.5 1059.42  4976.2 1057.58  4990.5 1057.67
  4995.4 1051.94  5000.0 1051.94  5006.7 1047.53  5007.0 1047.03  5011.3 1047.53
  5020.5 1050.18  5048.4 1055.36  5053.5 1053.00  5069.6 1055.11  5099.9 1051.11
  5119.3 1051.20  5124.3 1048.67  5130.2 1048.82  5150.4 1056.31  5160.5 1058.47
  5261.0 1058.89  5266.0 1056.00  5291.8 1059.94  5413.0 1063.17  5514.0 1070.80
#Mann=5,-1,0
  4034.1    0.12       0  4181.9    0.05       0  5006.7    0.05       0
  5011.3    0.05       0  5020.5    0.12       0
Bank Sta=5006.7,5011.3
Exp/Cntr=0.3,0.1

Type RM Length L Ch R = 1,5000,500,500,500
BEGIN DESCRIPTION:
COLORADO 06 10.0
END DESCRIPTION:
XS GIS Cut Line= 3
      2878155.68     10288003.12      2878207.68     10287604.50
      2877705.65     10287253.09
#Sta/Elev= 30
  4598.0 1066.64  4628.3 1064.83  4668.6 1064.53  4712.9 1061.64  4769.5 1052.77
  4910.6 1052.44  4971.1 1047.24  4991.3 1045.03  4998.2 1042.76  5007.5 1042.55
  5007.8 1042.05  5012.1 1042.55  5015.9 1045.56  5024.7 1047.24  5030.8 1052.11
  5045.6 1053.59  5051.7 1055.38  5066.5 1054.72  5138.0 1056.74  5283.2 1061.72
  5295.8 1062.31  5304.5 1064.19  5319.4 1063.31  5411.8 1066.34  5454.1 1069.92
  5504.2 1071.03  5533.9 1074.58  5569.6 1076.27  5599.2 1081.25  5612.8 1081.62
#Mann=4,-1,0
  4598.0    0.05       0  4712.9    0.12       0  5007.5    0.07       0
  5012.1    0.12       0
Bank Sta=5007.5,5012.1
Exp/Cntr=0.3,0.1

Type RM Length L Ch R = 1,4500,500,500,500
BEGIN DESCRIPTION:
COLORADO 06 9.0
END DESCRIPTION:
XS GIS Cut Line= 3
      2878605.70     10287753.14      2878488.98     10287496.21
      2878005.68     10287153.11
#Sta/Elev= 30
  4717.8 1064.64  4749.7 1062.90  4772.7 1059.37  4783.7 1055.19  4794.7 1053.73
  4806.8 1050.19  4837.8 1048.12  4922.2 1045.77  4950.7 1041.88  4991.4 1039.75
  4994.5 1037.54  4994.9 1037.04  4999.2 1037.54  5005.1 1038.47  5012.1 1044.92
  5018.2 1046.71  5068.6 1053.59  5077.3 1053.02  5126.7 1056.08  5184.3 1055.76
  5212.5 1057.62  5234.7 1055.20  5249.3 1055.52  5255.6 1057.13  5320.8 1058.09
  5356.5 1061.24  5407.0 1060.44  5543.5 1063.22  5579.2 1068.30  5592.7 1068.28
#Mann=4,-1,0
  4717.8    0.05       0  4837.8    0.12       0  4994.5    0.07       0
  4999.2    0.12       0
Bank Sta=4994.5,4999.2
Exp/Cntr=0.3,0.1

Type RM Length L Ch R = 1,4000,500,500,500
BEGIN DESCRIPTION:
COLORADO 06 8.0
END DESCRIPTION:
XS GIS Cut Line= 3
      2878755.70     10287703.08      2878931.52     10287302.79
      2878905.69     10286953.15
#Sta/Elev= 30
  4562.8 1055.84  4595.1 1053.16  4600.5 1053.55  4670.6 1049.06  4770.7 1044.17
  4827.1 1040.99  4956.0 1038.92  4988.7 1036.22  4996.6 1033.71  4996.9 1033.21
  5001.0 1033.21  5001.4 1033.71  5008.0 1034.85  5013.0 1034.52  5019.7 1038.07
  5024.0 1038.68  5049.8 1041.85  5089.9 1045.59  5100.0 1045.72  5130.0 1048.12
  5151.1 1048.33  5180.2 1047.15  5190.2 1045.99  5220.3 1038.76  5229.2 1037.67
  5260.4 1039.05  5279.1 1043.24  5284.1 1039.63  5330.6 1054.79  5350.6 1057.69
#Mann=6,-1,0
  4562.8    0.05       0  4770.7    0.12       0  4996.6    0.07       0
  5001.4    0.12       0  5024.0    0.05       0  5229.2    0.12       0
Bank Sta=4996.6,5001.4
Exp/Cntr=0.3,0.1