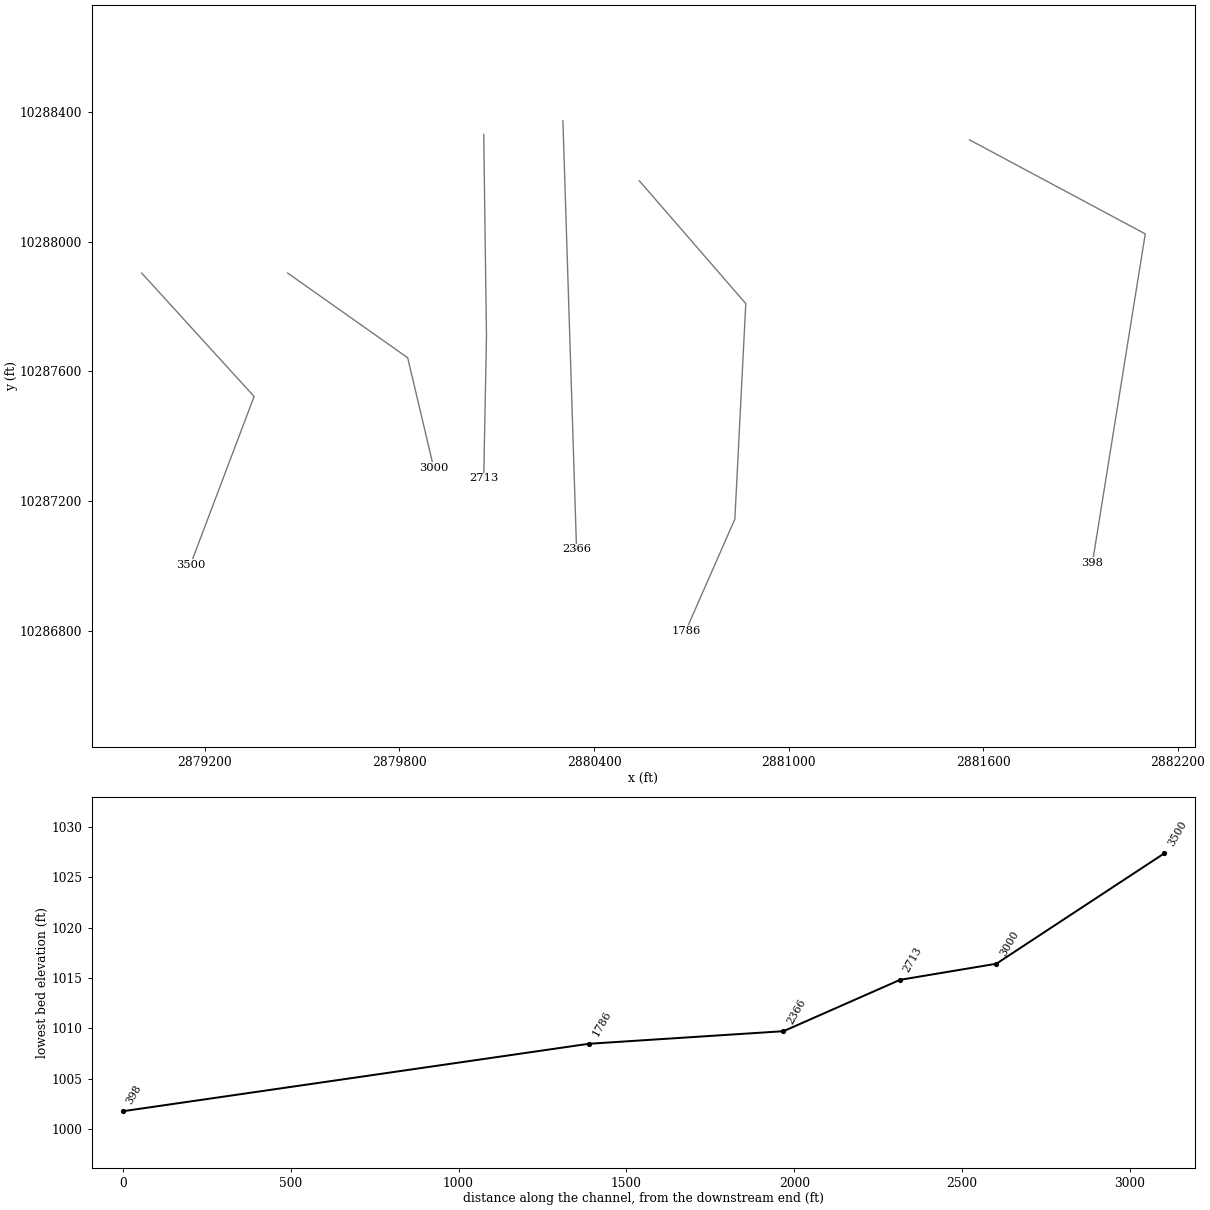
HEC-RAS study COLORADO 06.prj: COLORADO 06 Base Level Engineering

--- COLORADO 06.g01 (geometry) --- (continued)

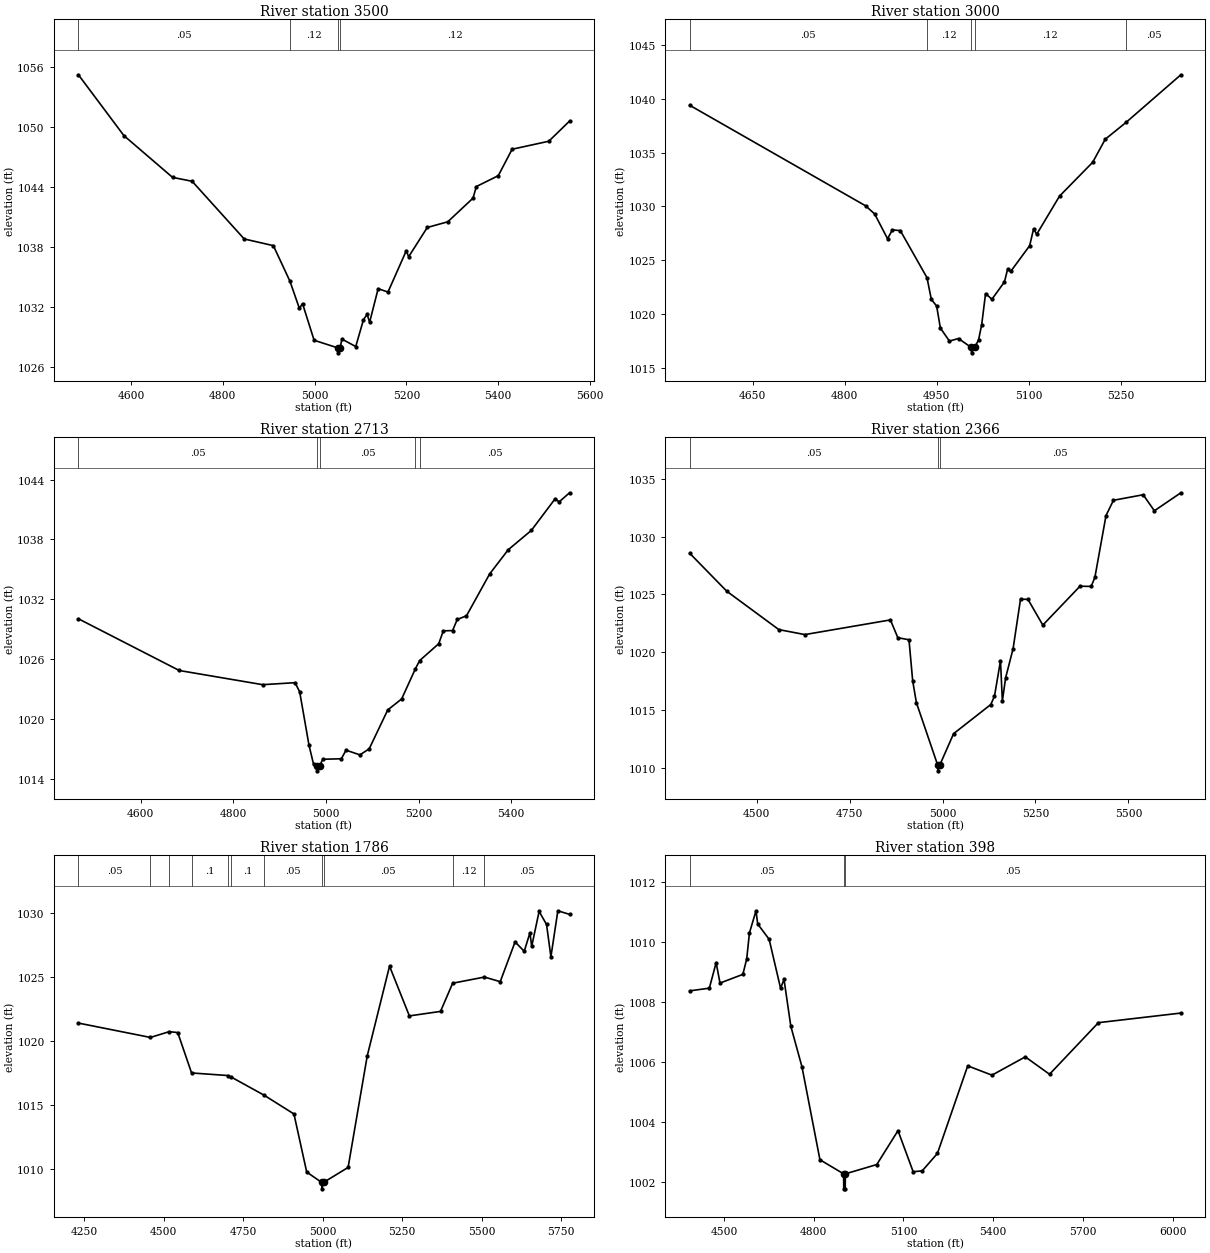
Type RM Length L Ch R = 1,3500,500,500,500
BEGIN DESCRIPTION:
COLORADO 06 7.0
END DESCRIPTION:
XS GIS Cut Line= 3
      2879005.67     10287903.13      2879352.11     10287522.61
      2879155.68     10287003.11
#Sta/Elev= 30
  4485.4 1055.24  4584.4 1049.15  4690.5 1044.96  4733.1 1044.57  4846.6 1038.79
  4910.1 1038.12  4946.3 1034.55  4966.8 1031.83  4973.6 1032.32  4998.9 1028.64
  5050.1 1027.88  5050.6 1027.38  5055.7 1027.88  5059.4 1028.76  5089.6 1028.01
  5106.4 1030.70  5114.4 1031.24  5119.8 1030.44  5138.4 1033.81  5159.8 1033.47
  5199.6 1037.60  5204.9 1037.01  5245.4 1039.94  5290.1 1040.51  5345.1 1042.88
  5352.3 1044.04  5400.1 1045.13  5430.3 1047.78  5510.1 1048.58  5555.4 1050.60
#Mann=4,-1,0
  4485.4    0.05       0  4946.3    0.12       0  5050.1    0.07       0
  5055.7    0.12       0
Bank Sta=5050.1,5055.7
Exp/Cntr=0.3,0.1

Type RM Length L Ch R = 1,3000,287,287,287
BEGIN DESCRIPTION:
COLORADO 06 6.0
END DESCRIPTION:
XS GIS Cut Line= 3
      2879455.65     10287903.14      2879825.55     10287641.99
      2879905.68     10287303.14
#Sta/Elev= 30
  4547.2 1039.39  4834.1 1030.06  4848.9 1029.30  4869.8 1027.01  4877.8 1027.83
  4890.7 1027.76  4934.2 1023.39  4941.2 1021.39  4949.9 1020.76  4956.0 1018.72
  4970.8 1017.51  4985.6 1017.75  5006.3 1016.92  5006.8 1016.42  5012.0 1016.92
  5018.3 1017.63  5023.4 1019.04  5029.7 1021.92  5040.0 1021.39  5060.5 1023.00
  5065.7 1024.19  5070.8 1023.98  5101.6 1026.36  5108.0 1027.92  5113.1 1027.42
  5150.3 1030.96  5204.4 1034.10  5224.9 1036.24  5258.8 1037.80  5348.2 1042.22
#Mann=5,-1,0
  4547.2    0.05       0  4934.2    0.12       0  5006.3    0.07       0
  5012.0    0.12       0  5258.8    0.05       0
Bank Sta=5006.3,5012
Exp/Cntr=0.3,0.1

Type RM Length L Ch R = 1,2713,347,347,347
BEGIN DESCRIPTION:
Mapping XS 026f2610
END DESCRIPTION:
XS GIS Cut Line= 3
      2880060.01     10288330.80      2880068.42     10287708.17
      2880060.01     10287270.64
#Sta/Elev= 30
  4465.7 1030.05  4683.4 1024.87  4863.4 1023.45  4933.4 1023.65  4943.4 1022.73
  4963.4 1017.41  4973.4 1015.46  4980.6 1015.32  4981.0 1014.82  4986.3 1015.32
  4993.4 1015.98  5033.4 1016.03  5043.4 1016.89  5073.4 1016.42  5093.4 1017.02
  5133.5 1020.92  5163.5 1022.02  5193.2 1025.04  5202.3 1025.86  5243.5 1027.55
  5253.5 1028.84  5273.5 1028.87  5283.5 1029.98  5303.5 1030.35  5353.5 1034.54
  5393.5 1036.96  5443.5 1038.90  5494.7 1042.06  5503.5 1041.76  5526.0 1042.67
#Mann=5,-1,0
  4465.7    0.05       0  4980.6    0.03       0  4986.3    0.05       0
  5193.2    0.12       0  5202.3    0.05       0
Bank Sta=4980.6,4986.3
Exp/Cntr=0.3,0.1

Type RM Length L Ch R = 1,2366,580,580,580
BEGIN DESCRIPTION:
Mapping XS a1686bdb
END DESCRIPTION:
XS GIS Cut Line= 2
      2880304.03     10288372.93      2880346.10     10287051.80
#Sta/Elev= 30
  4319.4 1028.56  4419.3 1025.27  4559.3 1021.95  4629.4 1021.52  4859.5 1022.79
  4879.5 1021.25  4909.5 1021.07  4919.5 1017.51  4929.5 1015.62  4986.7 1010.22
  4987.2 1009.72  4992.4 1010.22  5029.6 1012.94  5129.6 1015.46  5139.6 1016.18
  5155.8 1019.26  5160.8 1015.77  5169.7 1017.79  5189.7 1020.30  5209.7 1024.59
  5229.7 1024.57  5269.7 1022.34  5369.8 1025.71  5399.8 1025.69  5409.8 1026.47
  5439.8 1031.83  5459.8 1033.15  5539.8 1033.63  5569.9 1032.24  5641.2 1033.80
#Mann=3,-1,0
  4319.4    0.05       0  4986.7    0.03       0  4992.4    0.05       0
Bank Sta=4986.7,4992.4
Exp/Cntr=0.3,0.1

Type RM Length L Ch R = 1,1786,1388,1388,1388
BEGIN DESCRIPTION:
Mapping XS 6ae56fae
END DESCRIPTION:
XS GIS Cut Line= 4
      2880539.64     10288187.78      2880867.79     10287809.14
      2880834.14     10287144.40      2880682.68     10286799.43
#Sta/Elev= 30
  4232.6 1021.40  4458.8 1020.28  4517.9 1020.73  4544.7 1020.66  4588.2 1017.51
  4701.6 1017.31  4713.5 1017.18  4816.4 1015.77  4909.9 1014.31  4950.0 1009.78
  4997.1 1008.97  4997.6 1008.47  5002.9 1008.97  5080.1 1010.14  5140.2 1018.84
  5210.3 1025.84  5272.6 1021.96  5370.5 1022.31  5408.7 1024.51  5508.5 1024.99
  5558.1 1024.63  5604.8 1027.73  5633.6 1027.00  5651.5 1028.44  5657.0 1027.38
  5680.3 1030.11  5703.7 1029.09  5717.4 1026.57  5739.2 1030.16  5776.0 1029.88
#Mann=11,-1,0
  4232.6    0.05       0  4458.8     0.1       0  4517.9    0.05       0
  4588.2     0.1       0  4701.6    0.05       0  4713.5     0.1       0
  4816.4    0.05       0  4997.1    0.03       0  5002.9    0.05       0
  5408.7    0.12       0  5508.5    0.05       0
Bank Sta=4997.1,5002.9
Exp/Cntr=0.3,0.1

Type RM Length L Ch R = 1,398,0,0,0
BEGIN DESCRIPTION:
COLORADO 06 3.0
END DESCRIPTION:
XS GIS Cut Line= 3
      2881557.82     10288313.98      2882099.25     10288024.00
      2881936.43     10287009.79
#Sta/Elev= 30
  4385.8 1008.37  4451.4 1008.46  4474.1 1009.31  4487.1 1008.63  4563.4 1008.92
  4576.2 1009.43  4585.4 1010.30  4607.3 1011.04  4613.0 1010.60  4651.2 1010.09
  4689.4 1008.46  4701.0 1008.75  4723.7 1007.19  4760.9 1005.84  4821.0 1002.74
  4900.1 1002.27  4900.6 1001.77  4905.5 1001.77  4906.0 1002.27  5011.0 1002.58
  5081.9 1003.71  5132.6 1002.34  5162.9 1002.37  5213.6 1002.95  5314.9 1005.87
  5395.9 1005.56  5507.3 1006.17  5588.3 1005.59  5751.7 1007.31  6027.2 1007.63
#Mann=3,-1,0
  4385.8    0.05       0  4900.1    0.03       0  4906.0    0.05       0
Bank Sta=4900.1,4906
Exp/Cntr=0.3,0.1

Chan Stop Cuts=-1