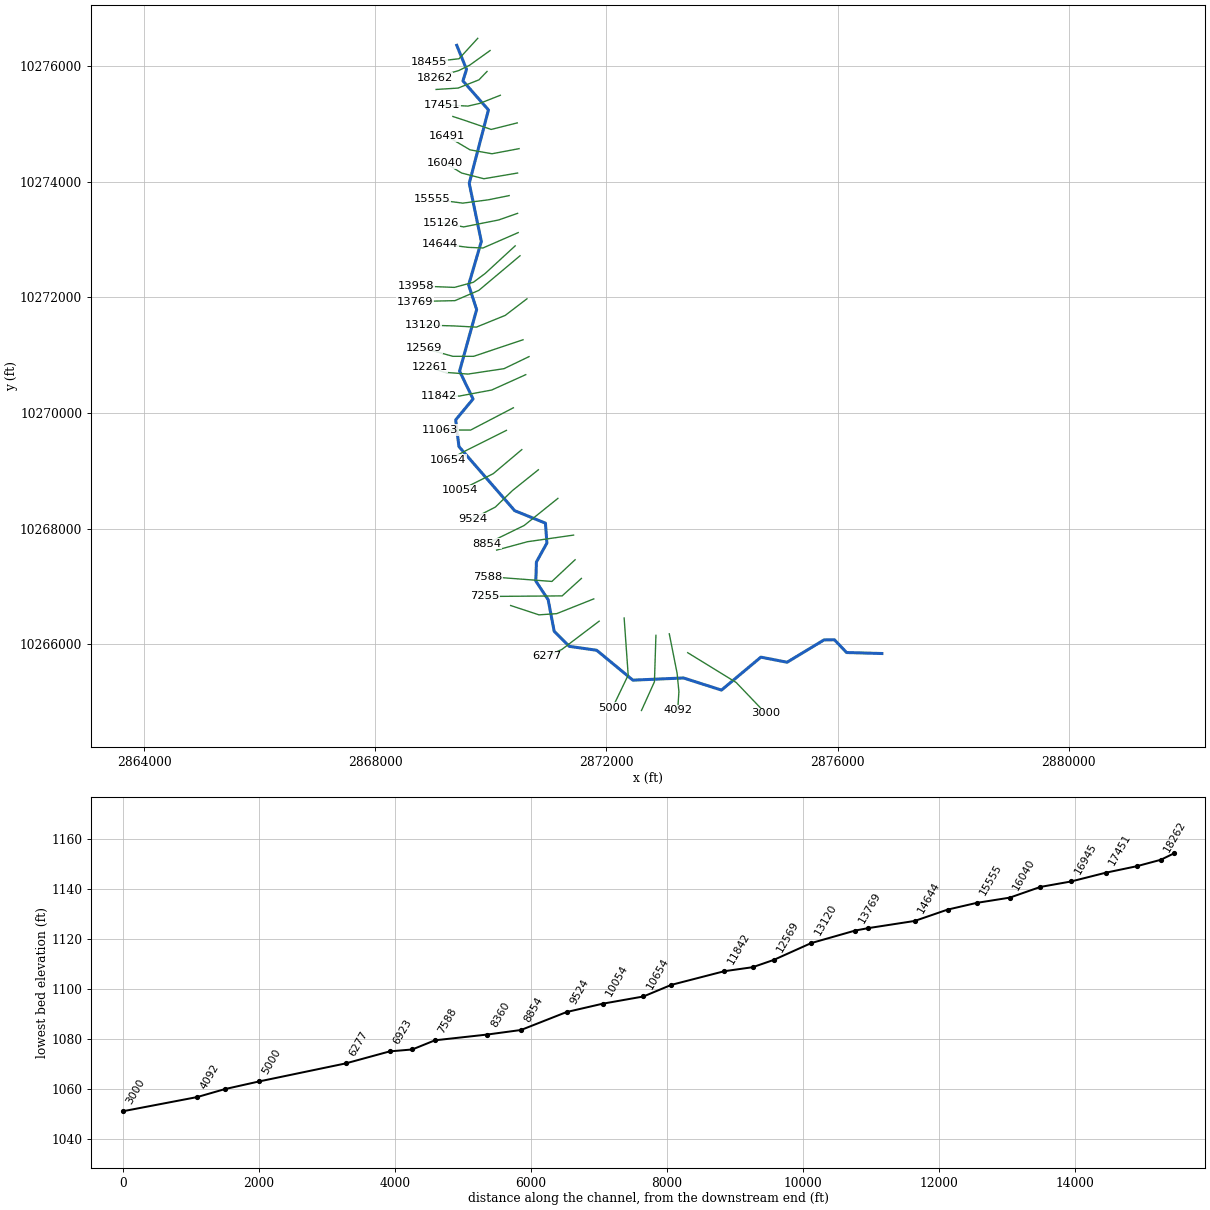
--- COLORADO 08.prj (project) ---

Proj Title=COLORADO 08 Base Level Engineering
Current Plan=p01
Default Exp/Contr=0.3,0.1
English Units
Geom File=g01
Flow File=f01
Plan File=p01
Y Axis Title=Elevation
X Axis Title(PF)=Main Channel Distance
X Axis Title(XS)=Station
BEGIN DESCRIPTION:
COLORADO 08
END DESCRIPTION:
DSS Export Rating Curves= 0
DSS Export Rating Curve Sorted= 0
DSS Export Volume Flow Curves= 0
DXF OffsetX= 0
DXF OffsetY= 0
DXF ScaleX= 1
DXF ScaleY= 10

--- COLORADO 08.p01 (plan) ---

Plan Title=Multiple Run
Short Identifier=Multiple
Geom File=g01
Flow File=f01
Subcritical Flow
K Sum by GR= 0
Std Step Tol= 0.01
Critical Tol= 0.01
Num of Std Step Trials= 20
Max Error Tol= 0.3
Flow Tol Ratio= 0.001
Split Flow NTrial= 30
Split Flow Tol= 0.02
Split Flow Ratio= 0.02
Log Output Level= 0
Friction Slope Method= 1
Unsteady Friction Slope Method= 2
Unsteady Bridges Friction Slope Method= 1
Parabolic Critical Depth
Global Vel Dist=  1 , 1 , 1
Global Log Level= 0
CheckData=True
Encroach Param= -1, 0, 0, 0
BEGIN DESCRIPTION:
Multiple Run
END DESCRIPTION:

--- COLORADO 08.f01 (steady flow) ---

Flow Title=Multiple
Number of Profiles=7
Profile Names=10-year,25-year,50-year,1pct_min,100-year,1pct_plu,500-year
River Rch & RM= COLORADO 08,Reach-1,18455
     365     589     648     379     710    1333     948
River Rch & RM= COLORADO 08,Reach-1,11063
     599     997    1096     659    1289    2521    1715
River Rch & RM= COLORADO 08,Reach-1,6277
     954    1636    1673    1089    2216    4510    2937
Boundary for River Rch & Prof#=COLORADO 08,Reach-1,1
Up Type=0
Dn Type=3
Dn Slope=0.005
Boundary for River Rch & Prof#=COLORADO 08,Reach-1,2
Up Type=0
Dn Type=3
Dn Slope=0.005
Boundary for River Rch & Prof#=COLORADO 08,Reach-1,3
Up Type=0
Dn Type=3
Dn Slope=0.005
Boundary for River Rch & Prof#=COLORADO 08,Reach-1,4
Up Type=0
Dn Type=3
Dn Slope=0.005
Boundary for River Rch & Prof#=COLORADO 08,Reach-1,5
Up Type=0
Dn Type=3
Dn Slope=0.005
Boundary for River Rch & Prof#=COLORADO 08,Reach-1,6
Up Type=0
Dn Type=3
Dn Slope=0.005
Boundary for River Rch & Prof#=COLORADO 08,Reach-1,7
Up Type=0
Dn Type=3
Dn Slope=0.005

--- COLORADO 08.g01 (geometry) ---

Geom Title=Existing Conditions

River Reach=COLORADO 08,Reach-1
Reach XY= 30
      2869409.00     10276364.00      2869578.25     10275948.00
      2869515.75     10275748.00      2869957.50     10275246.00
      2869625.00     10273976.00      2869834.50     10272970.00
      2869614.25     10272216.00      2869753.25     10271792.00
      2869458.00     10270726.00      2869691.00     10270244.00
      2869390.75     10269882.00      2869447.00     10269420.00
      2870411.25     10268311.00      2870943.75     10268095.00
      2870969.00     10267751.00      2870787.75     10267423.00
      2870777.50     10267093.00      2870990.75     10266770.00
      2871095.25     10266223.00      2871356.25     10265963.00
      2871831.25     10265895.00      2872456.75     10265378.00
      2873332.50     10265416.00      2873990.25     10265206.00
      2874672.00     10265776.00      2875125.00     10265688.00
      2875764.25     10266074.00      2875945.00     10266077.00
      2876155.25     10265856.00      2876765.75     10265839.00

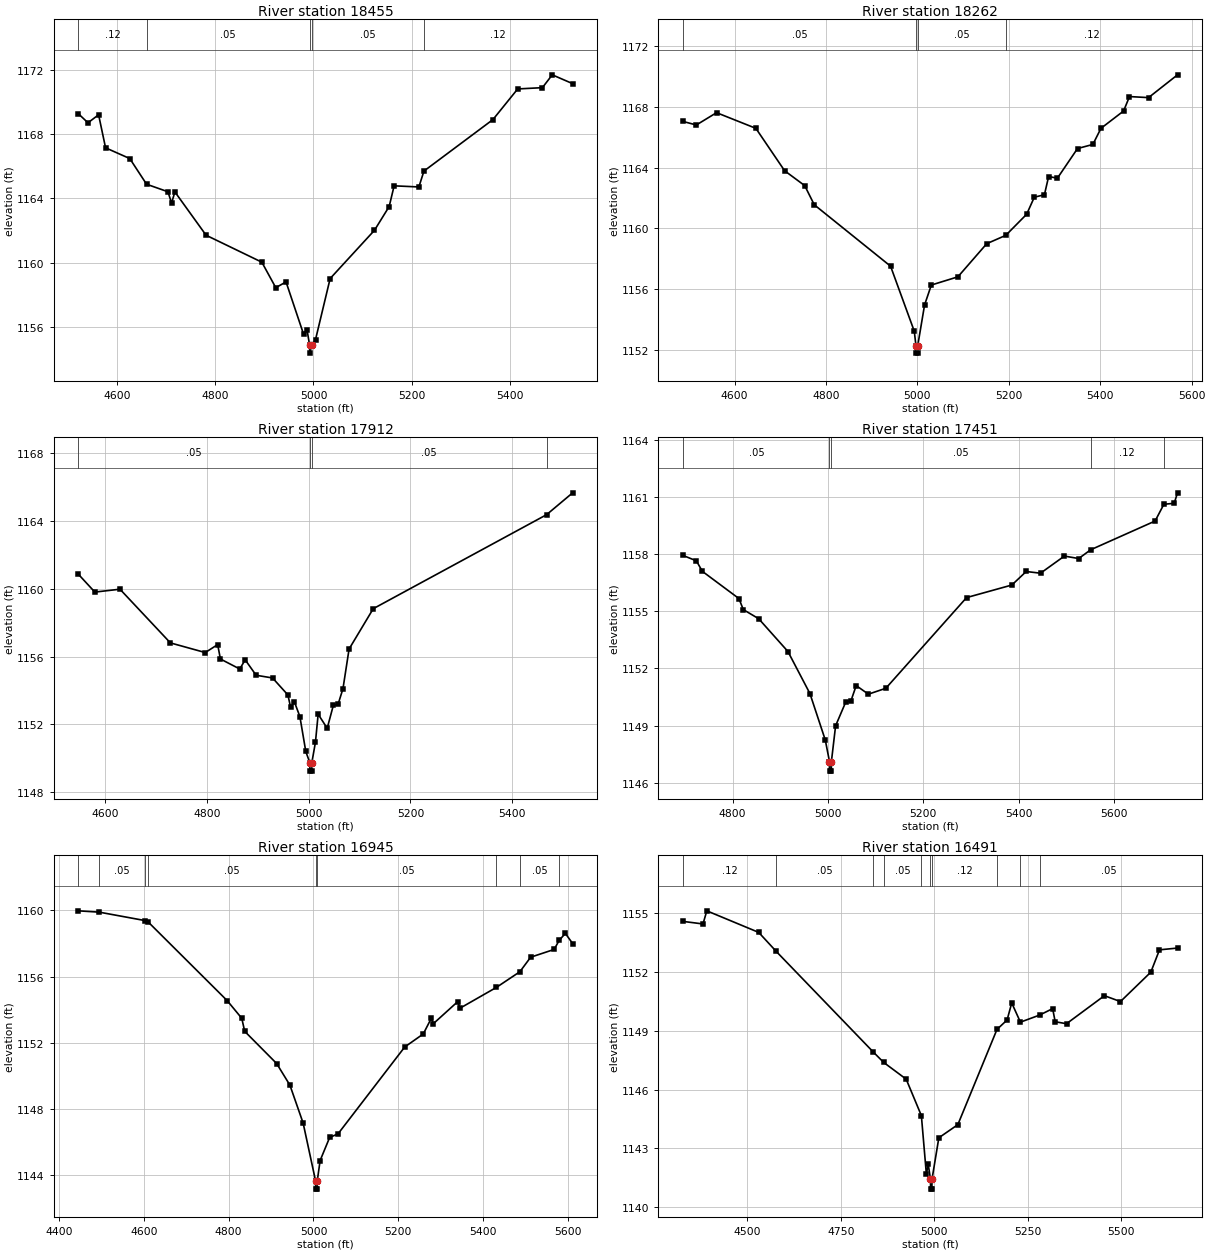
Type RM Length L Ch R = 1,18455,193,193,193
BEGIN DESCRIPTION:
COLORADO 08 37.0
END DESCRIPTION:
XS GIS Cut Line= 3
      2869772.16     10276484.81      2869448.88     10276131.36
      2868924.43     10276072.82
#Sta/Elev= 30
  4521.0 1169.29  4540.8 1168.72  4562.4 1169.22  4576.6 1167.16  4625.9 1166.49
  4660.1 1164.89  4703.6 1164.42  4711.0 1163.72  4717.8 1164.41  4781.3 1161.71
  4894.8 1160.03  4923.2 1158.44  4944.1 1158.80  4979.9 1155.53  4986.7 1155.83
  4992.1 1154.86  4992.3 1154.36  4996.1 1154.86  5004.1 1155.20  5033.9 1159.01
  5124.2 1162.02  5154.1 1163.50  5164.2 1164.79  5214.6 1164.72  5224.9 1165.71
  5365.4 1168.92  5415.8 1170.83  5466.1 1170.91  5486.2 1171.71  5527.7 1171.16
#Mann=5,-1,0
  4521.0    0.12       0  4660.1    0.05       0  4992.1    0.05       0
  4996.1    0.05       0  5224.9    0.12       0
Bank Sta=4992.1,4996.1
Exp/Cntr=0.3,0.1

Type RM Length L Ch R = 1,18262,350,350,350
BEGIN DESCRIPTION:
Mapping XS 71b7ca4b
END DESCRIPTION:
XS GIS Cut Line= 4
      2869986.12     10276273.56      2869632.19     10276019.99
      2869444.68     10275927.56      2869024.75     10275806.07
#Sta/Elev= 30
  4487.5 1167.04  4516.4 1166.81  4560.6 1167.62  4646.6 1166.59  4709.5 1163.80
  4753.5 1162.82  4774.4 1161.56  4941.3 1157.52  4993.2 1153.24  4996.8 1152.30
  4997.1 1151.80  5000.6 1151.80  5000.8 1152.30  5015.7 1154.97  5030.5 1156.28
  5088.6 1156.82  5151.7 1159.00  5193.4 1159.55  5239.1 1160.94  5255.8 1162.06
  5277.9 1162.22  5287.1 1163.42  5306.3 1163.31  5350.3 1165.26  5383.9 1165.53
  5401.6 1166.59  5451.1 1167.73  5464.0 1168.68  5505.7 1168.61  5569.1 1170.11
#Mann=4,-1,0
  4487.5    0.05       0  4996.8    0.05       0  5000.8    0.05       0
  5193.4    0.12       0
Bank Sta=4996.8,5000.8
Exp/Cntr=0.3,0.1

Type RM Length L Ch R = 1,17912,461,461,461
BEGIN DESCRIPTION:
Mapping XS 01581036
END DESCRIPTION:
XS GIS Cut Line= 4
      2869933.24     10275911.69      2869793.29     10275766.45
      2869431.47     10275623.84      2869051.12     10275600.07
#Sta/Elev= 30
  4547.0 1160.87  4579.6 1159.81  4629.0 1159.98  4728.1 1156.81  4796.6 1156.24
  4821.0 1156.71  4826.4 1155.86  4864.4 1155.27  4875.1 1155.81  4896.6 1154.90
  4928.9 1154.74  4959.0 1153.74  4964.4 1153.01  4971.8 1153.33  4982.6 1152.46
  4994.2 1150.40  5002.1 1149.74  5002.3 1149.24  5005.8 1149.24  5006.1 1149.74
  5013.2 1150.95  5018.5 1152.60  5036.3 1151.77  5048.3 1153.12  5057.8 1153.20
  5067.3 1154.11  5079.3 1156.45  5126.8 1158.83  5467.5 1164.38  5518.7 1165.67
#Mann=4,-1,0
  4547.0    0.05       0  5002.1    0.05       0  5006.1    0.05       0
  5467.5    0.12       0
Bank Sta=5002.1,5006.1
Exp/Cntr=0.3,0.1

Type RM Length L Ch R = 1,17451,506,506,506
BEGIN DESCRIPTION:
Mapping XS 6a6cba1c
END DESCRIPTION:
XS GIS Cut Line= 4
      2870163.06     10275499.72      2869809.14     10275359.74
      2869600.50     10275312.20      2869158.72     10275335.87
#Sta/Elev= 30
  4696.1 1157.93  4723.9 1157.65  4736.3 1157.10  4813.1 1155.67  4822.3 1155.09
  4854.6 1154.61  4915.9 1152.89  4962.1 1150.68  4994.3 1148.24  5003.1 1147.11
  5003.4 1146.61  5006.9 1146.61  5007.1 1147.11  5015.9 1148.99  5037.4 1150.25
  5048.1 1150.30  5059.1 1151.10  5084.7 1150.65  5121.3 1150.96  5290.6 1155.72
  5385.6 1156.38  5415.7 1157.09  5445.7 1157.00  5495.8 1157.90  5525.8 1157.77
  5550.9 1158.23  5686.1 1159.74  5704.5 1160.62  5726.1 1160.67  5733.1 1161.22
#Mann=5,-1,0
  4696.1    0.05       0  5003.1    0.05       0  5007.1    0.05       0
  5550.9    0.12       0  5704.5    0.05       0
Bank Sta=5003.1,5007.1
Exp/Cntr=0.3,0.1

Type RM Length L Ch R = 1,16945,454,454,454
BEGIN DESCRIPTION:
Mapping XS e2495552
END DESCRIPTION:
XS GIS Cut Line= 4
      2870456.20     10275021.69      2870004.57     10274908.12
      2869566.16     10275058.66      2869341.65     10275132.62
#Sta/Elev= 30
  4445.5 1159.98  4495.0 1159.90  4602.8 1159.39  4610.9 1159.29  4796.6 1154.54
  4831.0 1153.47  4837.9 1152.68  4913.2 1150.73  4944.5 1149.42  4975.7 1147.12
  5005.0 1143.62  5005.2 1143.12  5008.7 1143.12  5009.0 1143.62  5015.7 1144.85
  5038.2 1146.25  5058.0 1146.47  5215.2 1151.73  5258.9 1152.52  5277.7 1153.46
  5283.0 1153.15  5340.2 1154.48  5345.5 1154.08  5431.3 1155.34  5486.7 1156.29
  5512.1 1157.17  5567.4 1157.64  5579.6 1158.20  5593.9 1158.61  5611.1 1158.00
#Mann=9,-1,0
  4445.5    0.12       0  4495.0    0.05       0  4602.8    0.12       0
  4610.9    0.05       0  5005.0    0.05       0  5009.0    0.05       0
  5431.3    0.12       0  5486.7    0.05       0  5579.6    0.12       0
Bank Sta=5005,5009
Exp/Cntr=0.3,0.1

Type RM Length L Ch R = 1,16491,451,451,451
BEGIN DESCRIPTION:
Mapping XS ce3b96e8
END DESCRIPTION:
XS GIS Cut Line= 4
      2870487.88     10274575.86      2870019.18     10274487.33
      2869638.97     10274555.04      2869244.25     10274788.75
#Sta/Elev= 30
  4328.5 1154.58  4381.6 1154.45  4391.8 1155.12  4530.5 1154.02  4577.4 1153.05
  4836.7 1147.92  4864.4 1147.39  4924.9 1146.53  4965.5 1144.67  4978.8 1141.70
  4983.9 1142.18  4989.9 1141.42  4990.1 1140.92  4993.6 1140.92  4993.9 1141.42
  5012.2 1143.54  5063.0 1144.21  5167.7 1149.07  5194.7 1149.55  5207.1 1150.42
  5230.3 1149.44  5281.6 1149.80  5316.5 1150.13  5323.3 1149.46  5353.6 1149.36
  5454.9 1150.79  5497.8 1150.49  5579.0 1151.99  5602.2 1153.13  5650.4 1153.22
#Mann=10,-1,0
  4328.5    0.12       0  4577.4    0.05       0  4836.7    0.12       0
  4864.4    0.05       0  4965.5    0.12       0  4989.9    0.07       0
  4993.9    0.12       0  5167.7    0.05       0  5230.3    0.12       0
  5281.6    0.05       0
Bank Sta=4989.9,4993.9
Exp/Cntr=0.3,0.1

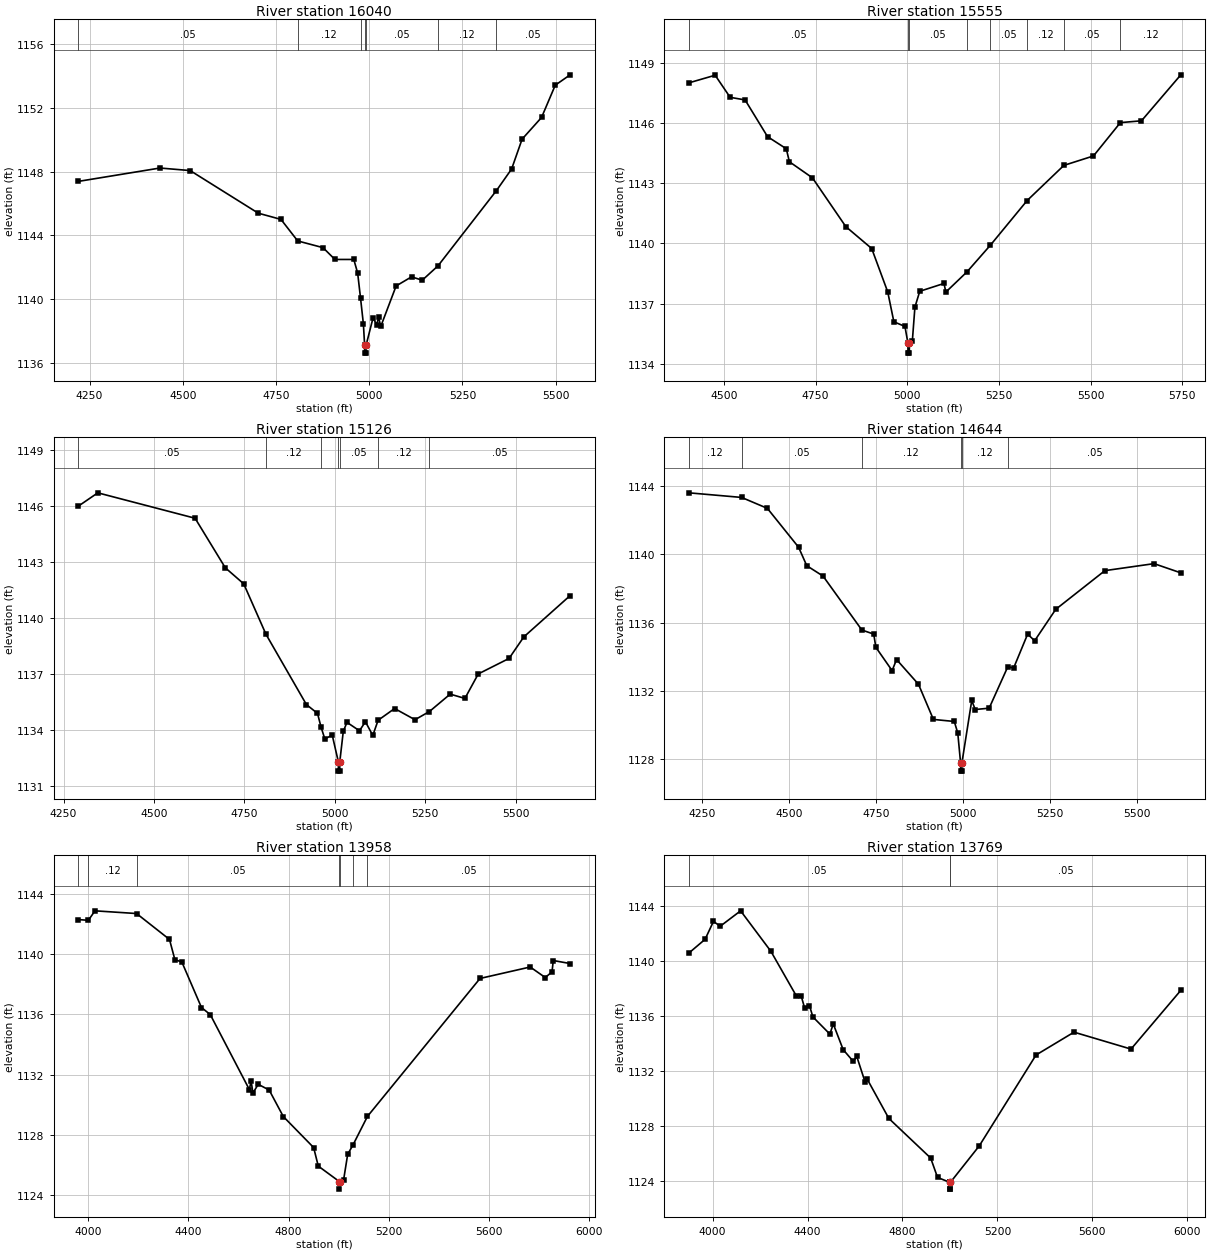
Type RM Length L Ch R = 1,16040,485,485,485
BEGIN DESCRIPTION:
Mapping XS ab0a7e46
END DESCRIPTION:
XS GIS Cut Line= 4
      2870461.90     10274154.00      2869878.55     10274055.04
      2869493.14     10274154.00      2869211.89     10274325.87
#Sta/Elev= 30
  4219.5 1147.38  4439.0 1148.22  4519.9 1148.06  4702.5 1145.39  4763.4 1145.00
  4808.3 1143.65  4876.1 1143.23  4908.1 1142.49  4958.7 1142.49  4969.0 1141.64
  4976.7 1140.08  4984.4 1138.45  4987.7 1137.12  4987.9 1136.62  4991.4 1136.62
  4991.7 1137.12  5010.3 1138.83  5020.0 1138.40  5025.2 1138.86  5031.0 1138.29
  5072.2 1140.83  5113.5 1141.40  5142.3 1141.19  5184.5 1142.09  5341.3 1146.81
  5381.9 1148.16  5410.0 1150.03  5462.2 1151.39  5498.9 1153.41  5538.7 1154.06
#Mann=7,-1,0
  4219.5    0.05       0  4808.3    0.12       0  4976.7    0.05       0
  4987.7    0.05       0  4991.7    0.05       0  5184.5    0.12       0
  5341.3    0.05       0
Bank Sta=4987.7,4991.7
Exp/Cntr=0.3,0.1

Type RM Length L Ch R = 1,15555,429,429,429
BEGIN DESCRIPTION:
Mapping XS bedcacb7
END DESCRIPTION:
XS GIS Cut Line= 4
      2870316.06     10273763.37      2869956.68     10273690.46
      2869513.97     10273633.16      2868989.30     10273700.69
#Sta/Elev= 30
  4404.1 1147.99  4475.8 1148.37  4516.7 1147.27  4557.5 1147.14  4618.8 1145.31
  4669.8 1144.71  4678.4 1144.06  4741.2 1143.26  4832.3 1140.83  4902.9 1139.74
  4946.6 1137.58  4963.4 1136.09  4993.6 1135.86  5001.7 1135.03  5002.0 1134.53
  5005.5 1134.53  5005.7 1135.03  5013.8 1135.14  5020.8 1136.82  5034.0 1137.61
  5100.1 1138.00  5105.2 1137.57  5163.0 1138.58  5226.9 1139.91  5327.0 1142.13
  5427.2 1143.88  5507.9 1144.35  5581.3 1146.01  5638.9 1146.10  5746.2 1148.39
#Mann=8,-1,0
  4404.1    0.05       0  5001.7    0.05       0  5005.7    0.05       0
  5163.0    0.12       0  5226.9    0.05       0  5327.0    0.12       0
  5427.2    0.05       0  5581.3    0.12       0
Bank Sta=5001.7,5005.7
Exp/Cntr=0.3,0.1

Type RM Length L Ch R = 1,15126,482,482,482
BEGIN DESCRIPTION:
Mapping XS af7a35ce
END DESCRIPTION:
XS GIS Cut Line= 4
      2870461.91     10273456.09      2870133.76     10273341.50
      2869529.59     10273221.71      2869139.84     10273294.46
#Sta/Elev= 30
  4290.3 1145.99  4344.7 1146.71  4613.6 1145.35  4697.1 1142.70  4748.1 1141.84
  4809.6 1139.14  4921.4 1135.38  4952.0 1134.91  4961.9 1134.17  4972.3 1133.54
  4992.7 1133.75  5009.6 1132.32  5009.9 1131.82  5013.4 1131.82  5013.6 1132.32
  5023.3 1133.95  5033.5 1134.43  5067.9 1133.98  5084.5 1134.46  5104.9 1133.73
  5119.5 1134.54  5165.2 1135.17  5221.5 1134.57  5261.5 1135.01  5318.8 1135.94
  5359.5 1135.71  5396.4 1137.02  5481.6 1137.85  5522.3 1139.00  5650.3 1141.21
#Mann=7,-1,0
  4290.3    0.05       0  4809.6    0.12       0  4961.9    0.05       0
  5009.6    0.05       0  5013.6    0.05       0  5119.5    0.12       0
  5261.5    0.05       0
Bank Sta=5009.6,5013.6
Exp/Cntr=0.3,0.1

Type RM Length L Ch R = 1,14644,686,686,686
BEGIN DESCRIPTION:
Mapping XS c59734d4
END DESCRIPTION:
XS GIS Cut Line= 4
      2870472.35     10273122.77      2869862.93     10272857.12
      2869607.72     10272867.54      2869119.40     10272929.88
#Sta/Elev= 30
  4213.1 1143.60  4364.6 1143.33  4438.5 1142.69  4528.2 1140.41  4551.6 1139.33
  4598.4 1138.72  4709.8 1135.56  4744.0 1135.32  4749.9 1134.55  4796.7 1133.18
  4809.4 1133.83  4872.4 1132.38  4915.2 1130.32  4975.2 1130.20  4985.2 1129.52
  4993.2 1127.79  4993.5 1127.29  4997.0 1127.29  4997.2 1127.79  5025.3 1131.43
  5035.3 1130.90  5075.3 1130.98  5128.9 1133.41  5145.5 1133.33  5185.8 1135.32
  5205.9 1134.93  5266.4 1136.77  5407.6 1139.04  5548.7 1139.45  5625.6 1138.91
#Mann=6,-1,0
  4213.1    0.12       0  4364.6    0.05       0  4709.8    0.12       0
  4993.2    0.07       0  4997.2    0.12       0  5128.9    0.05       0
Bank Sta=4993.2,4997.2
Exp/Cntr=0.3,0.1

Type RM Length L Ch R = 1,13958,189,189,189
BEGIN DESCRIPTION:
Mapping XS 35bfbba7
END DESCRIPTION:
XS GIS Cut Line= 5
      2870420.19     10272893.55      2869899.39     10272414.41
      2869696.26     10272263.37      2869368.14     10272174.83
      2868706.71     10272200.87
#Sta/Elev= 30
  3960.2 1142.30  4000.9 1142.25  4027.4 1142.88  4193.3 1142.70  4324.6 1140.98
  4346.1 1139.64  4374.0 1139.48  4452.2 1136.46  4487.3 1135.99  4643.3 1131.01
  4650.1 1131.59  4657.5 1130.78  4678.6 1131.36  4722.3 1130.98  4778.7 1129.22
  4899.7 1127.16  4918.2 1125.93  5002.5 1124.90  5002.7 1124.40  5006.5 1124.90
  5019.0 1124.99  5035.5 1126.71  5057.2 1127.35  5114.4 1129.23  5563.5 1138.39
  5763.7 1139.15  5823.8 1138.45  5850.7 1138.83  5855.7 1139.58  5922.8 1139.38
#Mann=7,-1,0
  3960.2    0.05       0  4000.9    0.12       0  4193.3    0.05       0
  5002.5    0.05       0  5006.5    0.05       0  5057.2    0.12       0
  5114.4    0.05       0
Bank Sta=5002.5,5006.5
Exp/Cntr=0.3,0.1

Type RM Length L Ch R = 1,13769,649,649,649
BEGIN DESCRIPTION:
Mapping XS e324b978
END DESCRIPTION:
XS GIS Cut Line= 4
      2870503.56     10272721.71      2869790.01     10272122.75
      2869378.55     10271945.66      2868685.89     10271930.04
#Sta/Elev= 30
  3900.2 1140.60  3968.6 1141.60  4003.8 1142.90  4032.4 1142.55  4118.2 1143.67
  4245.7 1140.73  4352.4 1137.50  4373.2 1137.49  4387.5 1136.63  4408.3 1136.78
  4422.6 1135.96  4494.2 1134.71  4508.5 1135.45  4550.2 1133.58  4593.0 1132.72
  4607.4 1133.09  4642.5 1131.23  4650.3 1131.47  4742.6 1128.58  4918.8 1125.70
  4947.8 1124.29  4998.3 1123.94  4998.5 1123.44  5002.0 1123.44  5002.3 1123.94
  5123.4 1126.58  5362.7 1133.19  5522.7 1134.85  5762.8 1133.62  5972.6 1137.89
#Mann=3,-1,0
  3900.2    0.05       0  4998.3    0.03       0  5002.3    0.05       0
Bank Sta=4998.3,5002.3
Exp/Cntr=0.3,0.1

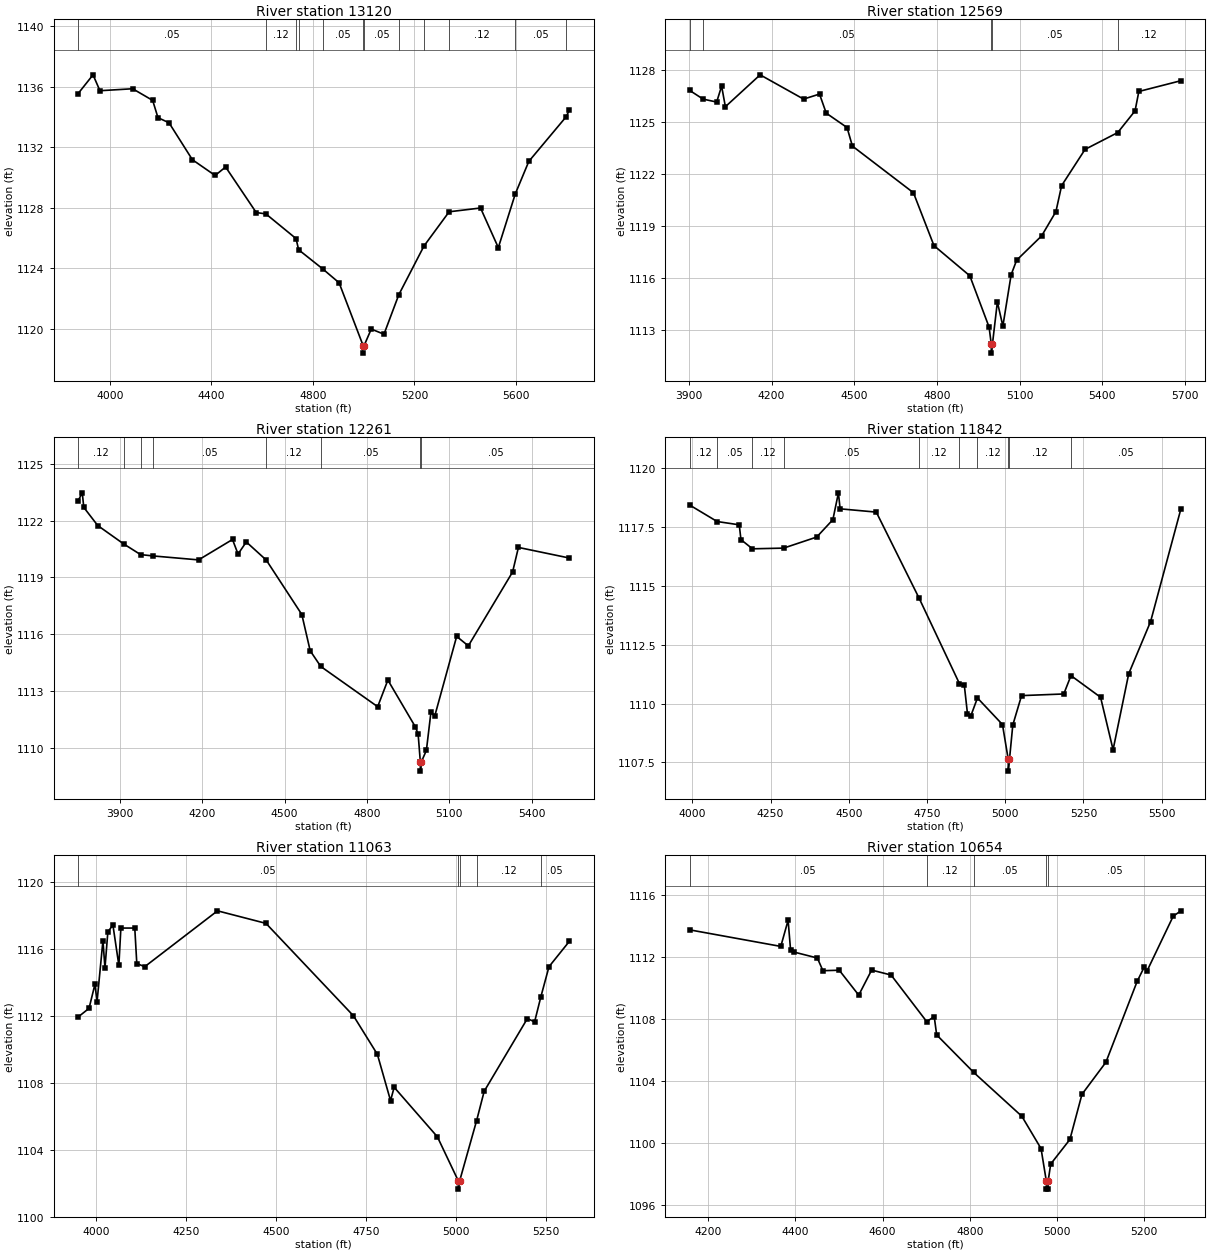
Type RM Length L Ch R = 1,13120,551,551,551
BEGIN DESCRIPTION:
Mapping XS 381a8e54
END DESCRIPTION:
XS GIS Cut Line= 5
      2870623.38     10271976.94      2870248.34     10271690.46
      2869748.34     10271487.33      2869357.72     10271508.16
      2868826.45     10271523.79
#Sta/Elev= 30
  3875.3 1135.55  3934.1 1136.79  3961.3 1135.74  4090.1 1135.87  4169.0 1135.10
  4189.8 1133.96  4233.4 1133.62  4325.4 1131.18  4414.9 1130.14  4456.2 1130.70
  4576.8 1127.69  4614.9 1127.60  4733.5 1125.97  4743.8 1125.23  4838.3 1123.97
  4903.1 1123.05  4997.7 1118.90  4998.0 1118.40  5001.7 1118.90  5029.8 1119.99
  5079.9 1119.65  5138.3 1122.26  5237.5 1125.48  5336.5 1127.74  5460.2 1127.99
  5530.2 1125.37  5597.0 1128.92  5650.3 1131.07  5797.9 1134.03  5809.6 1134.46
#Mann=12,-1,0
  3875.3    0.05       0  4614.9    0.12       0  4733.5    0.05       0
  4743.8    0.12       0  4838.3    0.05       0  4997.7    0.03       0
  5001.7    0.05       0  5138.3    0.12       0  5237.5    0.05       0
  5336.5    0.12       0  5597.0    0.05       0  5797.9    0.12       0
Bank Sta=4997.7,5001.7
Exp/Cntr=0.3,0.1

Type RM Length L Ch R = 1,12569,308,308,308
BEGIN DESCRIPTION:
Mapping XS e95782a9
END DESCRIPTION:
XS GIS Cut Line= 4
      2870555.59     10271268.57      2869701.47     10270982.12
      2869342.09     10270982.12      2868838.78     10271122.22
#Sta/Elev= 30
  3902.7 1126.80  3951.3 1126.30  4000.6 1126.13  4018.6 1127.05  4032.2 1125.86
  4158.4 1127.70  4316.1 1126.30  4373.9 1126.59  4398.3 1125.49  4473.8 1124.66
  4493.3 1123.59  4714.8 1120.90  4789.3 1117.85  4919.4 1116.11  4989.4 1113.15
  4997.4 1112.15  4997.6 1111.65  5001.4 1112.15  5019.4 1114.60  5039.4 1113.21
  5069.4 1116.17  5089.4 1117.01  5180.0 1118.41  5231.9 1119.81  5252.6 1121.31
  5337.7 1123.40  5456.3 1124.37  5519.1 1125.62  5532.9 1126.74  5685.4 1127.36
#Mann=5,-1,0
  3902.7    0.12       0  3951.3    0.05       0  4997.4    0.05       0
  5001.4    0.05       0  5456.3    0.12       0
Bank Sta=4997.4,5001.4
Exp/Cntr=0.3,0.1

Type RM Length L Ch R = 1,12261,419,419,419
BEGIN DESCRIPTION:
Mapping XS 45ca1f1a
END DESCRIPTION:
XS GIS Cut Line= 5
      2870659.76     10270976.89      2870227.51     10270768.58
      2869602.51     10270674.83      2869191.05     10270706.08
      2868941.03     10270794.63
#Sta/Elev= 30
  3747.7 1123.06  3762.9 1123.48  3768.4 1122.71  3819.2 1121.75  3913.3 1120.78
  3975.4 1120.21  4020.7 1120.14  4186.6 1119.93  4310.3 1121.01  4330.5 1120.24
  4360.6 1120.88  4433.4 1119.92  4562.9 1117.04  4593.4 1115.12  4631.9 1114.29
  4839.3 1112.16  4876.4 1113.57  4976.7 1111.09  4986.7 1110.71  4994.7 1109.25
  4995.0 1108.75  4998.7 1109.25  5016.8 1109.85  5033.4 1111.87  5046.9 1111.65
  5127.1 1115.88  5169.6 1115.38  5330.9 1119.29  5352.1 1120.59  5537.4 1120.03
#Mann=8,-1,0
  3747.7    0.12       0  3913.3    0.05       0  3975.4    0.12       0
  4020.7    0.05       0  4433.4    0.12       0  4631.9    0.05       0
  4994.7    0.05       0  4998.7    0.05       0
Bank Sta=4994.7,4998.7
Exp/Cntr=0.3,0.1

Type RM Length L Ch R = 1,11842,779,779,779
BEGIN DESCRIPTION:
Mapping XS 7f941cb1
END DESCRIPTION:
XS GIS Cut Line= 4
      2870602.50     10270664.41      2870013.97     10270398.79
      2869456.68     10270294.62      2869099.01     10270294.62
#Sta/Elev= 30
  3991.3 1118.44  4079.1 1117.74  4149.7 1117.60  4155.2 1116.97  4192.0 1116.58
  4291.7 1116.61  4397.4 1117.08  4449.1 1117.82  4466.8 1118.96  4472.2 1118.28
  4587.9 1118.14  4725.2 1114.47  4853.7 1110.85  4869.2 1110.79  4879.4 1109.57
  4889.6 1109.46  4911.3 1110.24  4991.3 1109.11  5009.7 1107.63  5009.9 1107.13
  5013.7 1107.63  5024.3 1109.09  5052.3 1110.34  5187.3 1110.41  5210.3 1111.19
  5304.9 1110.27  5344.9 1108.04  5394.9 1111.27  5464.9 1113.49  5561.6 1118.27
#Mann=10,-1,0
  3991.3    0.12       0  4079.1    0.05       0  4192.0    0.12       0
  4291.7    0.05       0  4725.2    0.12       0  4853.7    0.05       0
  4911.3    0.12       0  5009.7    0.07       0  5013.7    0.12       0
  5210.3    0.05       0
Bank Sta=5009.7,5013.7
Exp/Cntr=0.3,0.1

Type RM Length L Ch R = 1,11063,409,409,409
BEGIN DESCRIPTION:
Mapping XS f4792ede
END DESCRIPTION:
XS GIS Cut Line= 3
      2870388.97     10270091.50      2869649.39     10269706.08
      2869119.38     10269706.08
#Sta/Elev= 30
  3950.1 1111.94  3980.5 1112.46  3997.0 1113.91  4002.6 1112.83  4019.1 1116.51
  4024.7 1114.87  4032.7 1117.03  4046.8 1117.44  4063.3 1115.03  4068.9 1117.26
  4107.5 1117.26  4113.1 1115.14  4135.2 1114.95  4337.2 1118.29  4471.8 1117.54
  4714.9 1112.01  4781.2 1109.71  4817.8 1106.94  4827.8 1107.74  4947.8 1104.78
  5005.8 1102.15  5006.0 1101.65  5009.8 1102.15  5056.6 1105.73  5077.8 1107.50
  5197.8 1111.85  5217.8 1111.65  5235.2 1113.15  5257.8 1114.95  5314.1 1116.46
#Mann=5,-1,0
  3950.1    0.05       0  5005.8    0.03       0  5009.8    0.05       0
  5056.6    0.12       0  5235.2    0.05       0
Bank Sta=5005.8,5009.8
Exp/Cntr=0.3,0.1

Type RM Length L Ch R = 1,10654,600,600,600
BEGIN DESCRIPTION:
Mapping XS 1d3dd3ca
END DESCRIPTION:
XS GIS Cut Line= 3
      2870269.20     10269700.88      2869592.09     10269362.33
      2869264.01     10269190.47
#Sta/Elev= 30
  4157.3 1113.77  4366.4 1112.70  4383.2 1114.39  4388.8 1112.49  4396.0 1112.34
  4450.3 1111.95  4463.1 1111.13  4500.6 1111.16  4545.3 1109.55  4574.9 1111.17
  4619.6 1110.85  4701.3 1107.84  4718.6 1108.16  4724.2 1106.98  4809.4 1104.55
  4919.7 1101.72  4963.8 1099.63  4976.0 1097.51  4976.3 1097.01  4979.8 1097.01
  4980.0 1097.51  4985.9 1098.63  5030.0 1100.22  5057.7 1103.14  5112.6 1105.21
  5184.4 1110.44  5200.9 1111.38  5206.5 1111.08  5267.1 1114.65  5284.7 1115.00
#Mann=5,-1,0
  4157.3    0.05       0  4701.3    0.12       0  4809.4    0.05       0
  4976.0    0.05       0  4980.0    0.05       0
Bank Sta=4976,4980
Exp/Cntr=0.3,0.1

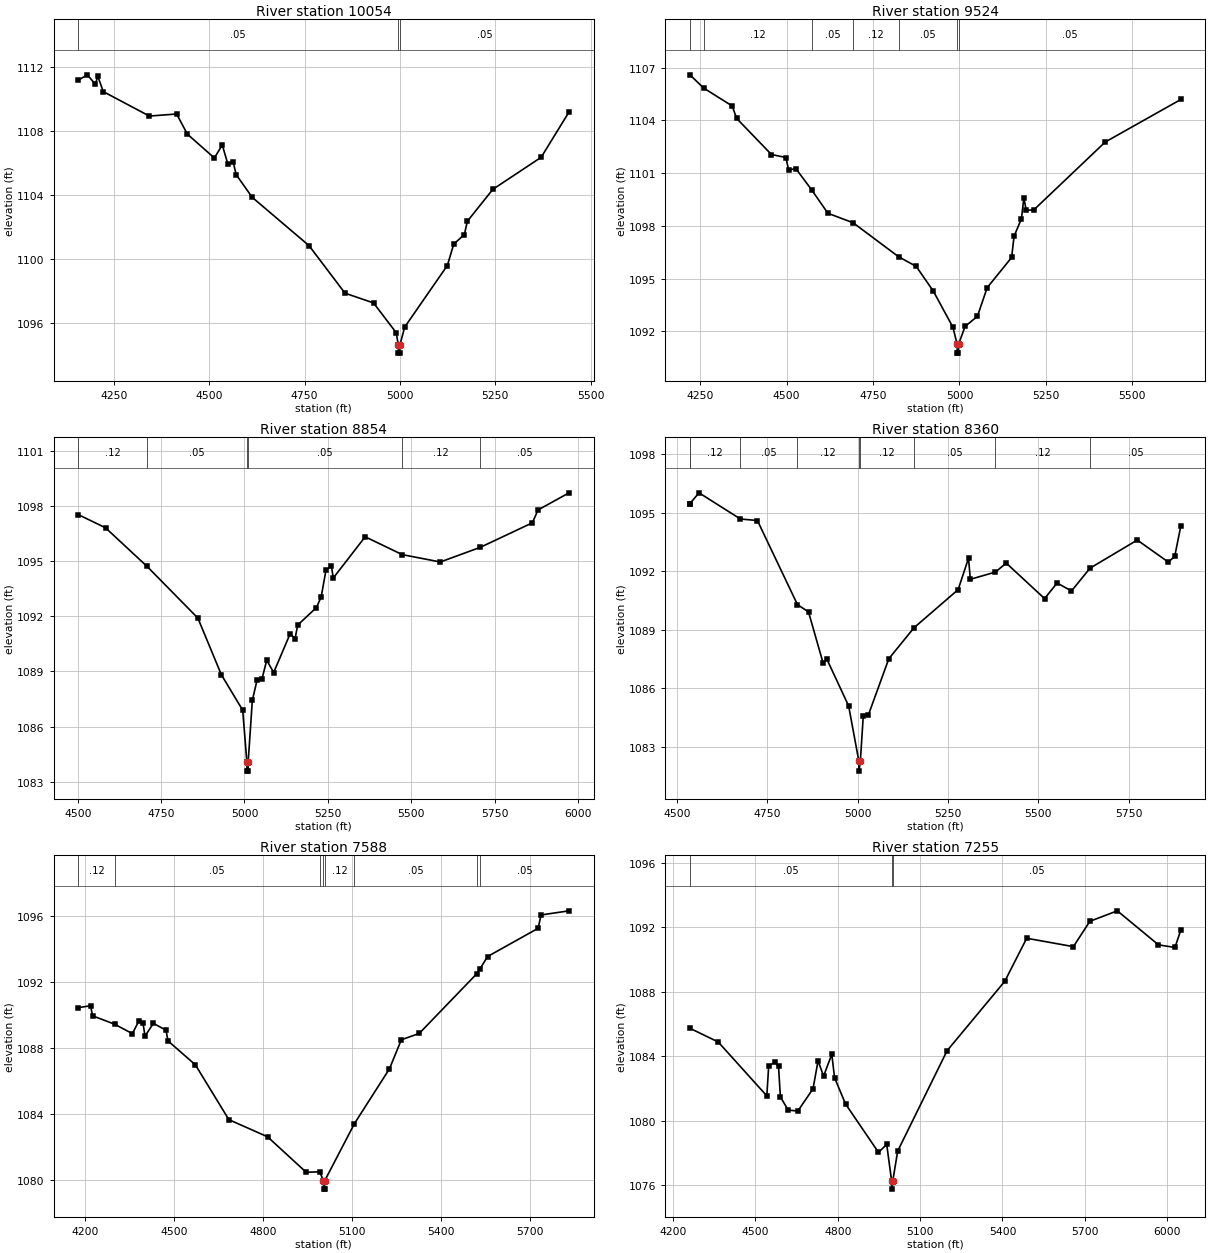
Type RM Length L Ch R = 1,10054,530,530,530
BEGIN DESCRIPTION:
Mapping XS fc06892f
END DESCRIPTION:
XS GIS Cut Line= 3
      2870534.81     10269367.55      2870040.01     10268950.87
      2869467.11     10268664.42
#Sta/Elev= 30
  4156.3 1111.18  4180.6 1111.52  4201.5 1110.93  4208.0 1111.43  4222.3 1110.47
  4343.2 1108.94  4414.7 1109.07  4442.8 1107.81  4513.6 1106.32  4534.4 1107.13
  4548.7 1105.96  4563.0 1106.06  4570.8 1105.28  4612.7 1103.86  4762.0 1100.83
  4856.2 1097.86  4931.0 1097.25  4990.4 1095.39  4996.1 1094.61  4996.3 1094.11
  4999.8 1094.11  5000.1 1094.61  5012.7 1095.74  5124.5 1099.59  5141.3 1100.93
  5169.2 1101.53  5177.0 1102.36  5244.0 1104.36  5370.5 1106.36  5443.7 1109.20
#Mann=3,-1,0
  4156.3    0.05       0  4996.1    0.05       0  5000.1    0.05       0
Bank Sta=4996.1,5000.1
Exp/Cntr=0.3,0.1

Type RM Length L Ch R = 1,9524,670,670,670
BEGIN DESCRIPTION:
Mapping XS 2d106d18
END DESCRIPTION:
XS GIS Cut Line= 4
      2870821.23     10269018.56      2870373.34     10268659.21
      2870076.47     10268372.75      2869691.08     10268174.85
#Sta/Elev= 30
  4220.4 1106.59  4260.1 1105.84  4342.7 1104.82  4355.7 1104.11  4456.3 1102.06
  4498.0 1101.89  4506.0 1101.18  4526.8 1101.26  4573.7 1100.02  4619.6 1098.72
  4692.5 1098.18  4823.9 1096.25  4875.0 1095.70  4924.6 1094.29  4981.2 1092.24
  4993.3 1091.27  4993.6 1090.77  4997.1 1090.77  4997.3 1091.27  5016.4 1092.29
  5051.9 1092.86  5080.2 1094.49  5151.0 1096.21  5157.9 1097.41  5179.3 1098.41
  5186.2 1099.58  5193.4 1098.88  5215.5 1098.92  5421.6 1102.77  5640.4 1105.19
#Mann=7,-1,0
  4220.4    0.05       0  4260.1    0.12       0  4573.7    0.05       0
  4692.5    0.12       0  4823.9    0.05       0  4993.3    0.03       0
  4997.3    0.05       0
Bank Sta=4993.3,4997.3
Exp/Cntr=0.3,0.1

Type RM Length L Ch R = 1,8854,494,494,494
BEGIN DESCRIPTION:
Mapping XS aa2b9516
END DESCRIPTION:
XS GIS Cut Line= 3
      2871159.77     10268523.76      2870576.47     10268055.04
      2869926.25     10267737.73
#Sta/Elev= 30
  4501.2 1097.53  4583.4 1096.81  4707.9 1094.71  4860.3 1091.90  4930.7 1088.82
  4994.7 1086.89  5007.1 1084.08  5007.4 1083.58  5010.9 1083.58  5011.1 1084.08
  5023.5 1087.42  5037.9 1088.55  5052.3 1088.58  5066.7 1089.61  5087.5 1088.94
  5137.1 1091.06  5151.5 1090.77  5159.5 1091.52  5215.5 1092.47  5229.9 1093.05
  5244.3 1094.51  5260.6 1094.72  5266.2 1094.08  5361.8 1096.32  5473.0 1095.35
  5587.1 1094.95  5707.3 1095.75  5863.0 1097.08  5880.0 1097.78  5973.0 1098.71
#Mann=6,-1,0
  4501.2    0.12       0  4707.9    0.05       0  5007.1    0.05       0
  5011.1    0.05       0  5473.0    0.12       0  5707.3    0.05       0
Bank Sta=5007.1,5011.1
Exp/Cntr=0.3,0.1

Type RM Length L Ch R = 1,8360,772,772,772
BEGIN DESCRIPTION:
Mapping XS 90ae4e57
END DESCRIPTION:
XS GIS Cut Line= 3
      2871430.65     10267888.37      2870633.76     10267773.79
      2870099.25     10267628.48
#Sta/Elev= 30
  4535.8 1095.47  4536.1 1095.47  4561.0 1096.02  4675.6 1094.68  4722.7 1094.60
  4833.6 1090.29  4864.1 1089.92  4904.5 1087.30  4914.6 1087.51  4975.2 1085.10
  5003.6 1082.26  5003.8 1081.76  5007.6 1082.26  5015.7 1084.60  5030.1 1084.65
  5086.4 1087.52  5156.4 1089.11  5278.3 1091.06  5307.0 1092.67  5312.1 1091.59
  5381.5 1091.96  5411.4 1092.42  5517.6 1090.60  5552.2 1091.40  5592.0 1090.99
  5643.4 1092.16  5774.1 1093.60  5860.2 1092.47  5877.8 1092.77  5894.8 1094.33
#Mann=9,-1,0
  4535.8    0.05       0  4536.1    0.12       0  4675.6    0.05       0
  4833.6    0.12       0  5003.6    0.07       0  5007.6    0.12       0
  5156.4    0.05       0  5381.5    0.12       0  5643.4    0.05       0
Bank Sta=5003.6,5007.6
Exp/Cntr=0.3,0.1

Type RM Length L Ch R = 1,7588,333,333,333
BEGIN DESCRIPTION:
Mapping XS 12ba879c
END DESCRIPTION:
XS GIS Cut Line= 3
      2871456.64     10267461.26      2871055.64     10267086.29
      2869951.48     10267169.62
#Sta/Elev= 30
  4176.0 1090.43  4218.0 1090.55  4224.9 1089.94  4299.4 1089.43  4359.2 1088.86
  4380.7 1089.62  4394.9 1089.51  4401.7 1088.71  4430.0 1089.48  4472.5 1089.07
  4479.4 1088.42  4571.7 1086.97  4684.6 1083.65  4815.2 1082.61  4945.6 1080.46
  4991.2 1080.49  5003.8 1079.94  5004.0 1079.44  5007.5 1079.44  5007.8 1079.94
  5108.3 1083.41  5226.4 1086.73  5266.5 1088.49  5326.7 1088.87  5521.1 1092.49
  5531.4 1092.77  5557.3 1093.53  5727.8 1095.24  5737.8 1096.05  5832.3 1096.30
#Mann=8,-1,0
  4176.0    0.12       0  4299.4    0.05       0  4991.2    0.12       0
  5003.8    0.07       0  5007.8    0.12       0  5108.3    0.05       0
  5521.1    0.12       0  5531.4    0.05       0
Bank Sta=5003.8,5007.8
Exp/Cntr=0.3,0.1

Type RM Length L Ch R = 1,7255,332,332,332
BEGIN DESCRIPTION:
Mapping XS d38db6b1
END DESCRIPTION:
XS GIS Cut Line= 3
      2871566.05     10267138.37      2871232.72     10266836.29
      2869894.20     10266825.87
#Sta/Elev= 30
  4261.4 1085.74  4364.6 1084.89  4541.6 1081.55  4548.4 1083.40  4570.0 1083.63
  4584.2 1083.38  4591.0 1081.49  4619.3 1080.67  4654.5 1080.61  4709.9 1081.99
  4728.3 1083.73  4748.3 1082.77  4778.3 1084.13  4788.3 1082.68  4828.3 1081.05
  4948.3 1078.05  4978.3 1078.54  4996.3 1076.27  4996.5 1075.77  5000.3 1076.27
  5018.3 1078.13  5198.3 1084.35  5408.3 1088.65  5488.3 1091.32  5658.3 1090.80
  5718.3 1092.37  5818.3 1093.02  5968.3 1090.91  6028.3 1090.75  6049.8 1091.84
#Mann=3,-1,0
  4261.4    0.05       0  4996.3    0.03       0  5000.3    0.05       0
Bank Sta=4996.3,5000.3
Exp/Cntr=0.3,0.1

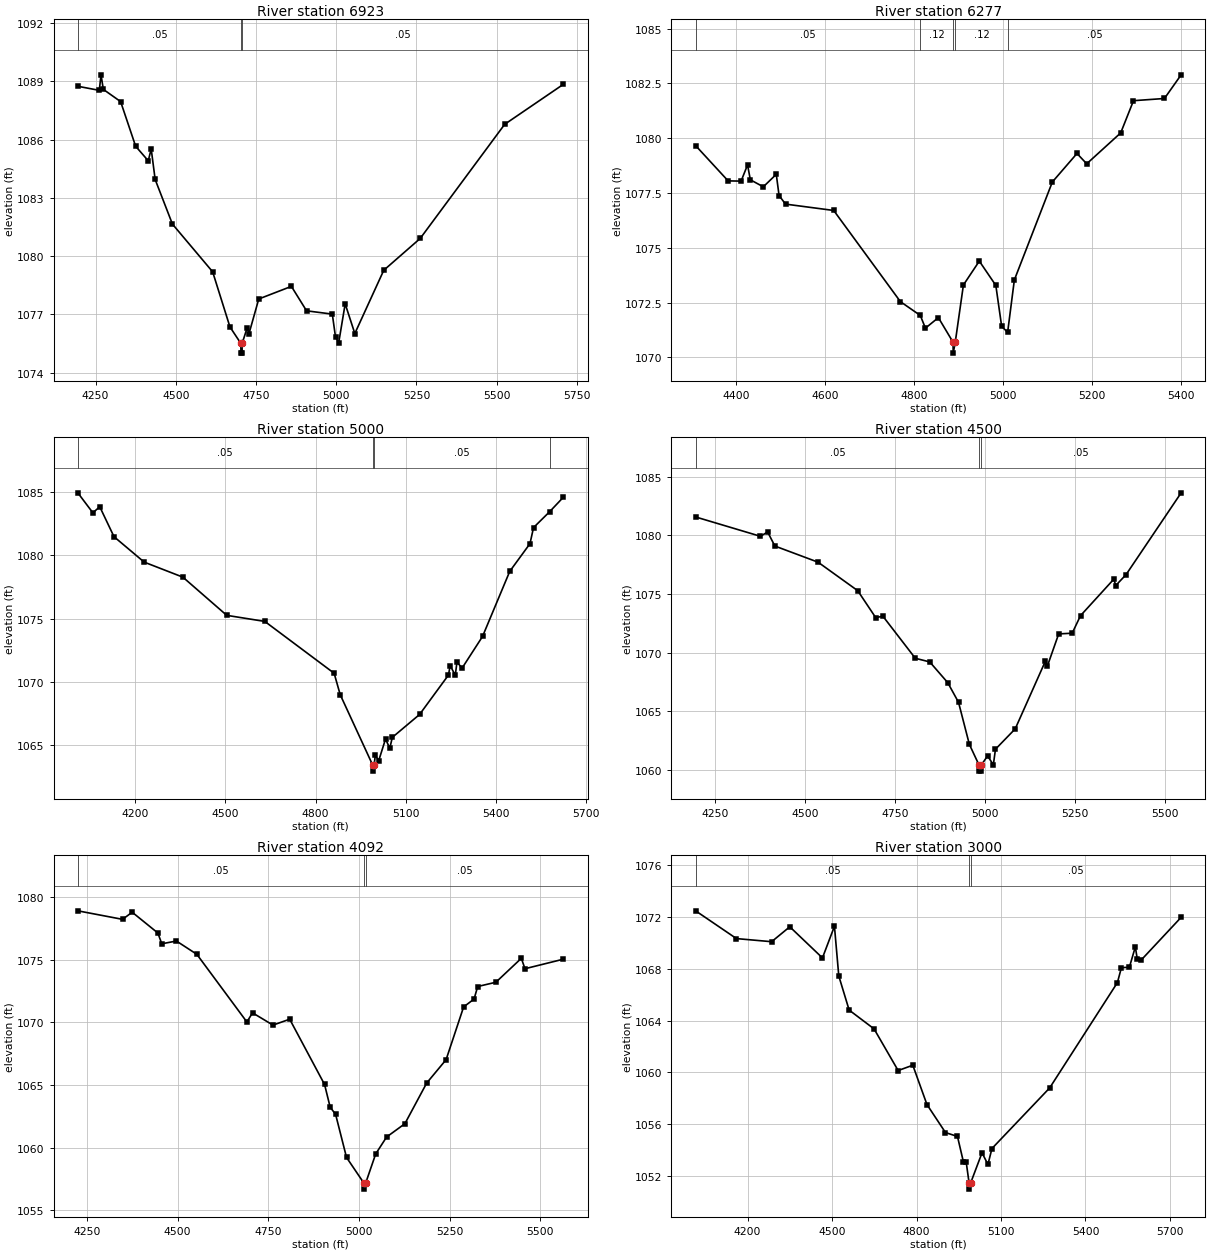
Type RM Length L Ch R = 1,6923,646,646,646
BEGIN DESCRIPTION:
Mapping XS c88e533f
END DESCRIPTION:
XS GIS Cut Line= 4
      2871779.58     10266784.20      2871138.97     10266529.00
      2870831.68     10266508.16      2870342.08     10266669.62
#Sta/Elev= 30
  4194.8 1088.75  4261.7 1088.54  4267.1 1089.34  4274.3 1088.59  4328.2 1087.96
  4375.0 1085.66  4414.3 1084.91  4423.5 1085.52  4435.8 1083.95  4489.6 1081.65
  4615.0 1079.19  4668.9 1076.35  4702.9 1075.50  4703.2 1075.00  4706.7 1075.00
  4706.9 1075.50  4722.9 1076.32  4728.2 1076.00  4758.7 1077.79  4860.4 1078.44
  4907.7 1077.18  4987.9 1077.01  4997.9 1075.83  5007.9 1075.54  5028.0 1077.54
  5058.1 1076.01  5148.3 1079.27  5261.9 1080.91  5525.1 1086.79  5707.9 1088.85
#Mann=3,-1,0
  4194.8    0.05       0  4702.9    0.05       0  4706.9    0.05       0
Bank Sta=4702.9,4706.9
Exp/Cntr=0.3,0.1

Type RM Length L Ch R = 1,6277,1277,1277,1277
BEGIN DESCRIPTION:
Mapping XS b253bd07
END DESCRIPTION:
XS GIS Cut Line= 3
      2871873.33     10266398.78      2871227.51     10265909.21
      2870972.27     10265794.61
#Sta/Elev= 30
  4309.8 1079.66  4382.8 1078.05  4411.9 1078.04  4426.4 1078.78  4432.7 1078.10
  4461.8 1077.78  4490.9 1078.35  4497.2 1077.38  4511.7 1076.99  4619.9 1076.70
  4769.6 1072.54  4814.3 1071.91  4825.8 1071.33  4854.9 1071.81  4887.8 1070.69
  4888.2 1070.19  4892.8 1070.69  4911.1 1073.30  4946.8 1074.39  4983.9 1073.28
  4997.0 1071.41  5010.4 1071.14  5025.5 1073.53  5110.8 1078.00  5166.1 1079.30
  5188.0 1078.83  5264.3 1080.24  5293.0 1081.71  5362.5 1081.81  5400.0 1082.89
#Mann=5,-1,0
  4309.8    0.05       0  4814.3    0.12       0  4887.8    0.07       0
  4892.8    0.12       0  5010.4    0.05       0
Bank Sta=4887.8,4892.8
Exp/Cntr=0.3,0.1

Type RM Length L Ch R = 1,5000,500,500,500
BEGIN DESCRIPTION:
COLORADO 08 10.0
END DESCRIPTION:
XS GIS Cut Line= 3
      2872305.68     10266453.12      2872375.86     10265465.31
      2872105.70     10264903.15
#Sta/Elev= 30
  4009.7 1084.95  4059.8 1083.37  4082.6 1083.85  4130.0 1081.48  4230.3 1079.47
  4359.0 1078.28  4504.8 1075.26  4631.3 1074.78  4861.8 1070.68  4881.9 1068.99
  4989.5 1063.44  4989.9 1062.94  4994.9 1063.44  4998.6 1064.19  5010.0 1063.77
  5032.6 1065.48  5046.8 1064.75  5055.2 1065.61  5145.8 1067.42  5241.9 1070.54
  5247.4 1071.29  5264.5 1070.52  5270.1 1071.56  5287.2 1071.09  5355.1 1073.59
  5445.6 1078.74  5512.8 1080.93  5524.6 1082.20  5578.3 1083.46  5623.7 1084.60
#Mann=4,-1,0
  4009.7    0.05       0  4989.5    0.05       0  4994.9    0.05       0
  5578.3    0.12       0
Bank Sta=4989.5,4994.9
Exp/Cntr=0.3,0.1

Type RM Length L Ch R = 1,4500,408,408,408
BEGIN DESCRIPTION:
COLORADO 08 9.0
END DESCRIPTION:
XS GIS Cut Line= 3
      2872855.69     10266153.14      2872830.05     10265349.55
      2872605.68     10264853.10
#Sta/Elev= 30
  4196.0 1081.58  4376.1 1079.93  4396.1 1080.30  4416.1 1079.10  4536.2 1077.72
  4646.3 1075.29  4696.3 1072.99  4716.3 1073.11  4806.3 1069.52  4846.4 1069.21
  4896.4 1067.44  4926.4 1065.76  4956.4 1062.18  4983.6 1060.39  4984.1 1059.89
  4988.8 1059.89  4989.2 1060.39  5007.1 1061.19  5023.1 1060.43  5029.0 1061.76
  5083.9 1063.50  5167.3 1069.25  5172.8 1068.82  5204.6 1071.60  5242.1 1071.66
  5265.3 1073.16  5357.7 1076.27  5363.2 1075.73  5391.8 1076.66  5544.8 1083.64
#Mann=3,-1,0
  4196.0    0.05       0  4983.6    0.05       0  4989.2    0.05       0
Bank Sta=4983.6,4989.2
Exp/Cntr=0.3,0.1

Type RM Length L Ch R = 1,4092,1092,1092,1092
BEGIN DESCRIPTION:
Mapping XS 4de0afa1
END DESCRIPTION:
XS GIS Cut Line= 4
      2873086.88     10266180.07      2873222.30     10265497.75
      2873253.55     10265180.04      2873232.75     10264857.59
#Sta/Elev= 30
  4225.2 1078.90  4348.5 1078.22  4375.0 1078.79  4445.8 1077.13  4456.6 1076.27
  4496.9 1076.49  4553.2 1075.43  4691.1 1070.03  4706.7 1070.76  4763.0 1069.78
  4809.1 1070.25  4905.2 1065.04  4920.7 1063.22  4935.5 1062.67  4965.7 1059.22
  5013.1 1057.19  5013.6 1056.69  5018.7 1057.19  5046.1 1059.50  5076.2 1060.85
  5126.5 1061.91  5186.7 1065.16  5240.1 1067.02  5288.4 1071.23  5317.2 1071.86
  5327.2 1072.86  5377.3 1073.20  5447.4 1075.11  5457.5 1074.28  5563.2 1075.04
#Mann=3,-1,0
  4225.2    0.05       0  5013.1    0.05       0  5018.7    0.05       0
Bank Sta=5013.1,5018.7
Exp/Cntr=0.3,0.1

Type RM Length L Ch R = 1,3000,500,500,500
BEGIN DESCRIPTION:
COLORADO 08 6.0
END DESCRIPTION:
XS GIS Cut Line= 3
      2873405.67     10265853.12      2874244.51     10265337.95
      2874755.66     10264803.14
#Sta/Elev= 30
  4015.6 1072.46  4160.6 1070.32  4285.5 1070.08  4350.0 1071.23  4466.0 1068.83
  4508.6 1071.27  4524.0 1067.44  4560.8 1064.81  4649.3 1063.36  4734.8 1060.15
  4786.9 1060.56  4837.1 1057.53  4902.9 1055.37  4945.5 1055.07  4966.8 1053.09
  4976.3 1053.12  4986.6 1051.51  4987.1 1051.01  4992.7 1051.51  5032.7 1053.81
  5053.7 1052.91  5067.9 1054.14  5272.9 1058.81  5513.5 1066.93  5527.7 1068.08
  5556.0 1068.11  5577.1 1069.68  5584.3 1068.71  5598.5 1068.68  5739.8 1071.96
#Mann=3,-1,0
  4015.6    0.05       0  4986.6    0.03       0  4992.7    0.05       0
Bank Sta=4986.6,4992.7
Exp/Cntr=0.3,0.1