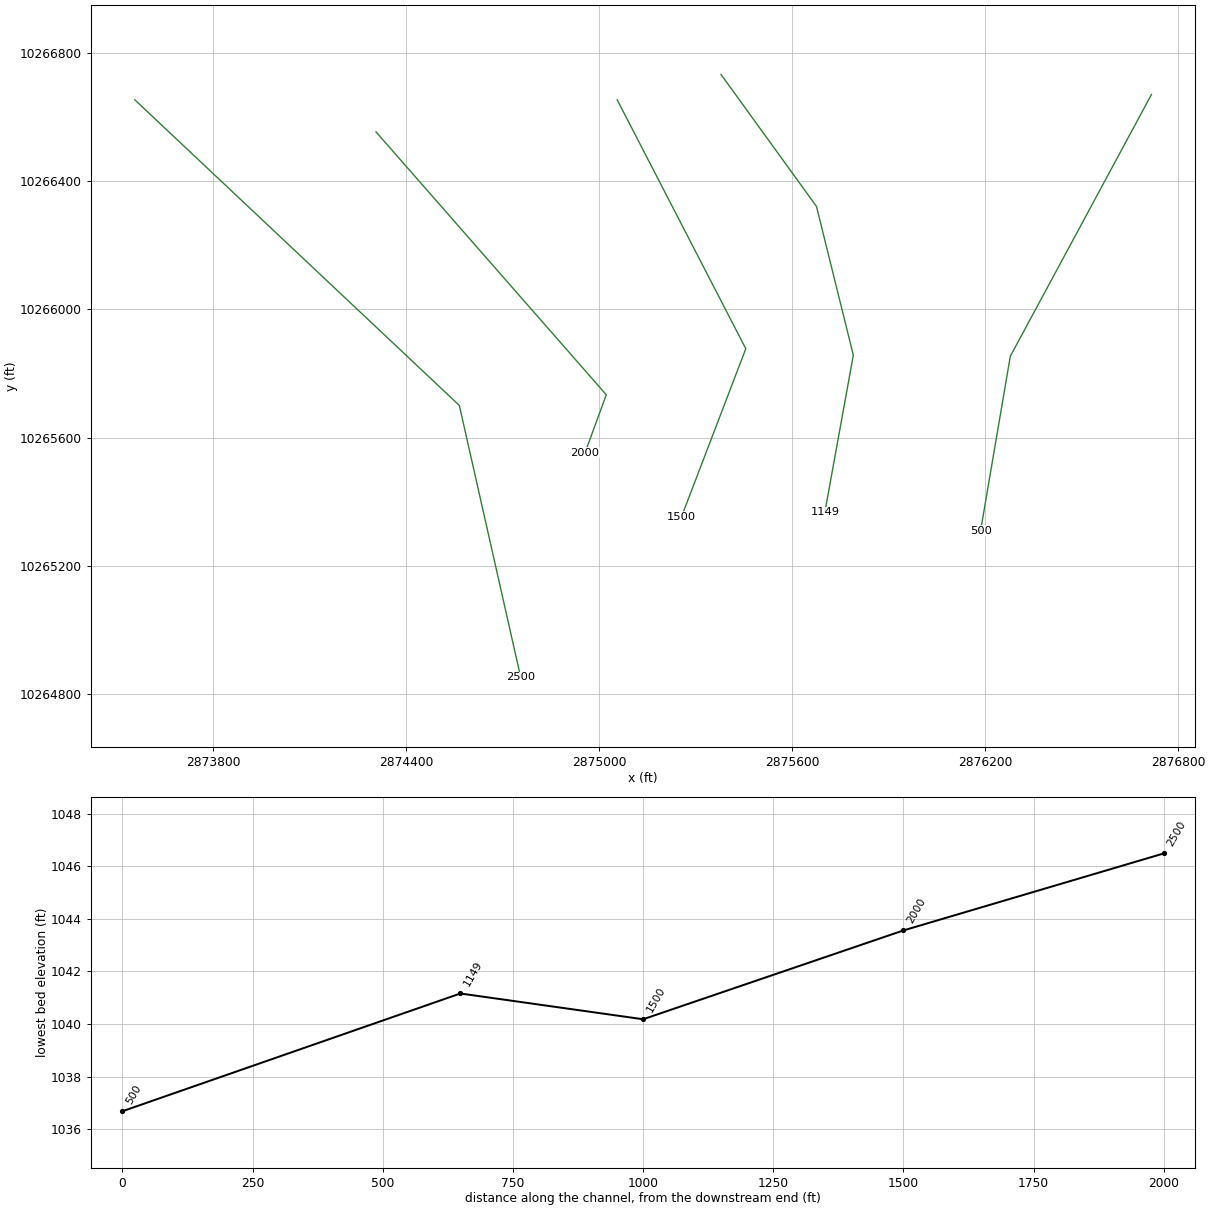
HEC-RAS study COLORADO 08.prj: COLORADO 08 Base Level Engineering

--- COLORADO 08.g01 (geometry) --- (continued)

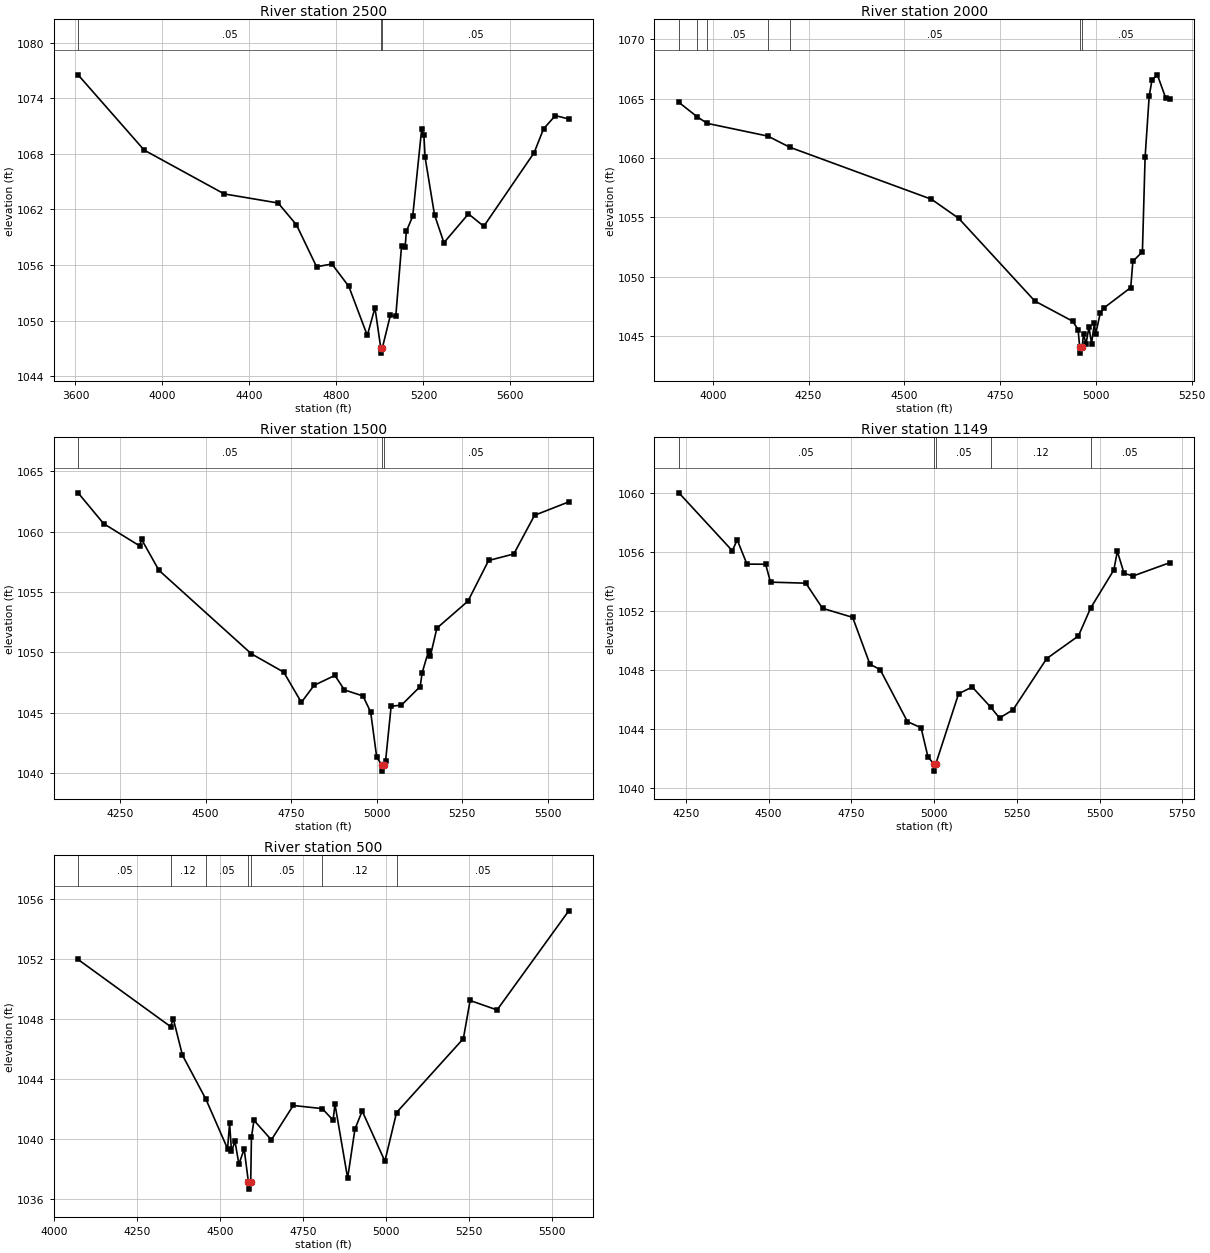
Type RM Length L Ch R = 1,2500,500,500,500
BEGIN DESCRIPTION:
COLORADO 08 5.0
END DESCRIPTION:
XS GIS Cut Line= 3
      2873555.68     10266653.11      2874564.89     10265700.35
      2874755.69     10264853.06
#Sta/Elev= 30
  3612.1 1076.54  3916.1 1068.41  4284.3 1063.68  4531.9 1062.70  4616.4 1060.34
  4708.7 1055.82  4779.5 1056.11  4857.1 1053.69  4942.1 1048.40  4977.3 1051.39
  5004.3 1046.99  5004.8 1046.49  5010.6 1046.99  5048.4 1050.60  5073.0 1050.46
  5099.7 1058.10  5116.2 1057.92  5121.4 1059.63  5150.9 1061.27  5191.9 1070.64
  5202.2 1070.03  5207.9 1067.63  5251.1 1061.43  5294.4 1058.41  5407.2 1061.53
  5477.7 1060.18  5709.4 1068.14  5752.6 1070.71  5806.9 1072.14  5868.5 1071.77
#Mann=3,-1,0
  3612.1    0.05       0  5004.3    0.03       0  5010.6    0.05       0
Bank Sta=5004.3,5010.6
Exp/Cntr=0.3,0.1

Type RM Length L Ch R = 1,2000,500,500,500
BEGIN DESCRIPTION:
COLORADO 08 4.0
END DESCRIPTION:
XS GIS Cut Line= 3
      2874305.67     10266553.13      2875021.89     10265733.59
      2874955.70     10265553.15
#Sta/Elev= 30
  3911.6 1064.68  3959.9 1063.45  3985.8 1062.91  4143.7 1061.84  4201.1 1060.90
  4570.8 1056.52  4642.0 1054.91  4840.4 1047.95  4939.1 1046.25  4953.4 1045.55
  4957.6 1044.06  4958.1 1043.56  4964.0 1044.06  4967.6 1045.14  4974.2 1044.35
  4981.8 1045.76  4988.5 1044.36  4996.1 1046.11  4999.1 1045.15  5011.2 1046.92
  5021.8 1047.39  5090.8 1049.08  5096.4 1051.29  5121.3 1052.10  5128.3 1060.05
  5139.0 1065.21  5146.5 1066.59  5160.3 1067.00  5182.3 1065.03  5192.2 1064.99
#Mann=7,-1,0
  3911.6    0.05       0  3959.9    0.12       0  3985.8    0.05       0
  4143.7    0.12       0  4201.1    0.05       0  4957.6    0.05       0
  4964.0    0.05       0
Bank Sta=4957.6,4964
Exp/Cntr=0.3,0.1

Type RM Length L Ch R = 1,1500,351,351,351
BEGIN DESCRIPTION:
COLORADO 08 3.0
END DESCRIPTION:
XS GIS Cut Line= 3
      2875055.69     10266653.09      2875455.67     10265877.22
      2875255.67     10265353.08
#Sta/Elev= 30
  4127.1 1063.21  4201.8 1060.66  4307.0 1058.82  4312.6 1059.36  4363.3 1056.80
  4633.4 1049.89  4728.1 1048.37  4779.6 1045.87  4816.8 1047.28  4877.6 1048.10
  4905.4 1046.90  4959.6 1046.40  4982.1 1045.07  4999.5 1041.39  5014.0 1040.68
  5014.5 1040.18  5020.4 1040.68  5025.8 1041.04  5041.9 1045.55  5072.0 1045.64
  5126.8 1047.18  5132.8 1048.34  5151.6 1050.15  5156.9 1049.74  5175.6 1052.01
  5266.5 1054.25  5326.7 1057.61  5400.4 1058.15  5461.0 1061.35  5561.0 1062.46
#Mann=3,-1,0
  4127.1    0.05       0  5014.0    0.05       0  5020.4    0.05       0
Bank Sta=5014,5020.4
Exp/Cntr=0.3,0.1

Type RM Length L Ch R = 1,1149,649,649,649
BEGIN DESCRIPTION:
Mapping XS 1c2411a6
END DESCRIPTION:
XS GIS Cut Line= 4
      2875378.53     10266732.15      2875675.43     10266320.66
      2875790.01     10265857.12      2875701.53     10265367.87
#Sta/Elev= 30
  4229.3 1059.98  4390.7 1056.06  4405.4 1056.80  4434.8 1055.16  4491.3 1055.15
  4506.0 1053.94  4612.8 1053.87  4663.1 1052.17  4754.1 1051.56  4806.3 1048.39
  4837.0 1048.03  4919.6 1044.51  4960.8 1044.09  4981.4 1042.14  4998.6 1041.66
  4999.1 1041.16  5005.4 1041.66  5074.1 1046.39  5115.3 1046.85  5171.4 1045.48
  5197.7 1044.75  5238.6 1045.31  5340.2 1048.77  5436.0 1050.30  5473.0 1052.19
  5543.0 1054.76  5553.6 1056.02  5574.0 1054.53  5601.6 1054.36  5711.4 1055.25
#Mann=5,-1,0
  4229.3    0.05       0  4998.6    0.05       0  5005.4    0.05       0
  5171.4    0.12       0  5473.0    0.05       0
Bank Sta=4998.6,5005.4
Exp/Cntr=0.3,0.1

Type RM Length L Ch R = 1,500,0,0,0
BEGIN DESCRIPTION:
COLORADO 08 1.0
END DESCRIPTION:
XS GIS Cut Line= 3
      2876717.08     10266669.60      2876278.13     10265853.56
      2876185.84     10265310.24
#Sta/Elev= 30
  4073.4 1051.97  4352.0 1047.50  4360.1 1048.02  4387.7 1045.60  4458.5 1042.66
  4523.6 1039.37  4529.7 1041.08  4535.4 1039.20  4546.0 1039.86  4557.7 1038.34
  4573.6 1039.35  4586.2 1037.18  4586.7 1036.68  4593.3 1037.18  4595.5 1040.14
  4603.1 1041.26  4655.5 1039.96  4721.3 1042.25  4808.7 1042.04  4841.4 1041.27
  4847.0 1042.34  4885.2 1037.41  4907.1 1040.67  4929.0 1041.88  4997.4 1038.54
  5032.5 1041.78  5233.7 1046.70  5254.0 1049.24  5335.2 1048.61  5551.1 1055.21
#Mann=7,-1,0
  4073.4    0.05       0  4352.0    0.12       0  4458.5    0.05       0
  4586.2    0.07       0  4593.3    0.05       0  4808.7    0.12       0
  5032.5    0.05       0
Bank Sta=4586.2,4593.3
Exp/Cntr=0.3,0.1

Chan Stop Cuts=-1