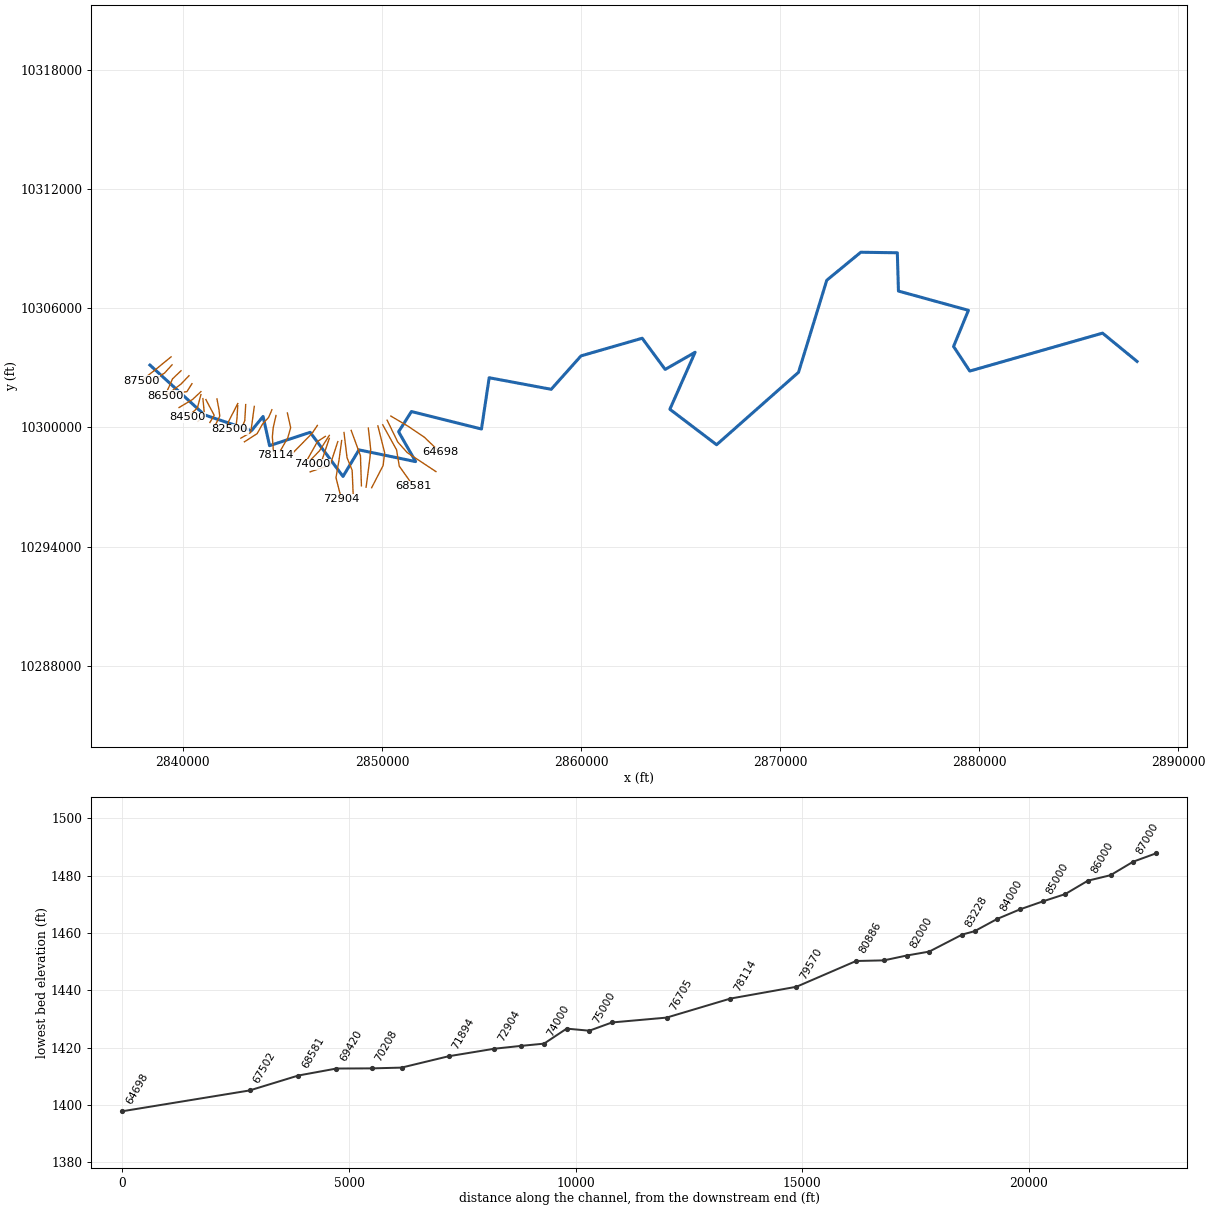
--- FALL CREEK.prj (project) ---

Proj Title=FALL CREEK Base Level Engineering
Current Plan=p01
Default Exp/Contr=0.3,0.1
English Units
Geom File=g01
Flow File=f01
Plan File=p01
Y Axis Title=Elevation
X Axis Title(PF)=Main Channel Distance
X Axis Title(XS)=Station
BEGIN DESCRIPTION:
FALL CREEK
END DESCRIPTION:
DSS Export Rating Curves= 0
DSS Export Rating Curve Sorted= 0
DSS Export Volume Flow Curves= 0
DXF OffsetX= 0
DXF OffsetY= 0
DXF ScaleX= 1
DXF ScaleY= 10

--- FALL CREEK.p01 (plan) ---

Plan Title=Multiple Run
Short Identifier=Multiple
Geom File=g01
Flow File=f01
Subcritical Flow
K Sum by GR= 0
Std Step Tol= 0.01
Critical Tol= 0.01
Num of Std Step Trials= 20
Max Error Tol= 0.3
Flow Tol Ratio= 0.001
Split Flow NTrial= 30
Split Flow Tol= 0.02
Split Flow Ratio= 0.02
Log Output Level= 0
Friction Slope Method= 1
Unsteady Friction Slope Method= 2
Unsteady Bridges Friction Slope Method= 1
Parabolic Critical Depth
Global Vel Dist=  1 , 1 , 1
Global Log Level= 0
CheckData=True
Encroach Param= -1, 0, 0, 0
BEGIN DESCRIPTION:
Multiple Run
END DESCRIPTION:

--- FALL CREEK.f01 (steady flow) ---

Flow Title=Multiple
Number of Profiles=7
Profile Names=10-year,25-year,50-year,1pct_min,100-year,1pct_plu,500-year
River Rch & RM= FALL CREEK,Reach-1,87500
     335     537     590     364     629    1086     835
River Rch & RM= FALL CREEK,Reach-1,82500
     696    1152    1186     853    1539    2775    2003
River Rch & RM= FALL CREEK,Reach-1,78114
     941    1593    1752    1045    1994    3805    2575
River Rch & RM= FALL CREEK,Reach-1,74000
     989    1682    1850    1036    2001    3866    2571
River Rch & RM= FALL CREEK,Reach-1,72904
    1446    2514    2765    1629    3216    6349    4123
River Rch & RM= FALL CREEK,Reach-1,67502
    1904    3379    3717    2067    4255    8762    5441
River Rch & RM= FALL CREEK,Reach-1,61050
    2270    4094    4503    2427    5192   11108    6665
River Rch & RM= FALL CREEK,Reach-1,53268
    2579    4739    5032    3175    6870   14864    8877
River Rch & RM= FALL CREEK,Reach-1,46500
    2837    5269    5534    3409    7587   16890    9826
River Rch & RM= FALL CREEK,Reach-1,37500
    2959    5535    6158    3822    8517   18977   11047
River Rch & RM= FALL CREEK,Reach-1,35000
    3158    5949    7029    4371    9810   22015   12776
River Rch & RM= FALL CREEK,Reach-1,30500
    3253    6145    7356    4557   10294   23255   13436
River Rch & RM= FALL CREEK,Reach-1,27500
    3461    6569    8289    5153   11675   26454   15264
River Rch & RM= FALL CREEK,Reach-1,23500
    5058    9563   13933   11404   19755   34220   25657
River Rch & RM= FALL CREEK,Reach-1,15500
    5064    9576   13947   11419   19776   34248   25685
River Rch & RM= FALL CREEK,Reach-1,14500
    5298   10022   14663   11978   20803   36129   27020
River Rch & RM= FALL CREEK,Reach-1,9500
    5273    9981   14562   11921   20664   35819   26839
River Rch & RM= FALL CREEK,Reach-1,5989
    5410   10238   14982   12241   21263   36934   27615
River Rch & RM= FALL CREEK,Reach-1,4000
    5479   10359   15179   12383   21533   37443   27947
Boundary for River Rch & Prof#=FALL CREEK,Reach-1,1
Up Type=0
Dn Type=3
Dn Slope=0.005
Boundary for River Rch & Prof#=FALL CREEK,Reach-1,2
Up Type=0
Dn Type=3
Dn Slope=0.005
Boundary for River Rch & Prof#=FALL CREEK,Reach-1,3
Up Type=0
Dn Type=3
Dn Slope=0.005
Boundary for River Rch & Prof#=FALL CREEK,Reach-1,4
Up Type=0
Dn Type=3
Dn Slope=0.005
Boundary for River Rch & Prof#=FALL CREEK,Reach-1,5
Up Type=0
Dn Type=3
Dn Slope=0.005
Boundary for River Rch & Prof#=FALL CREEK,Reach-1,6
Up Type=0
Dn Type=3
Dn Slope=0.005
Boundary for River Rch & Prof#=FALL CREEK,Reach-1,7
Up Type=0
Dn Type=3
Dn Slope=0.005

--- FALL CREEK.g01 (geometry) ---

Geom Title=Existing Conditions
Program Version=4.00

River Reach=FALL CREEK      ,Reach-1
Reach XY= 30
        2838344.       10303140.       2841083.5       10300635.
      2843444.25       10299839.       2844028.5       10300555.
       2844353.5       10299087.       2846394.5       10299756.
      2848043.75       10297538.        2848847.       10298874.
       2851692.5       10298284.        2850838.       10299786.
      2851481.75       10300802.       2855000.5       10299924.
        2855388.       10302502.       2858503.5       10301921.
       2860001.5       10303601.      2863075.75       10304489.
        2864229.       10302920.      2865734.75       10303783.
        2864466.       10300918.        2866813.       10299133.
        2870930.       10302777.      2872348.25       10307404.
      2874057.75       10308814.       2875893.5       10308787.
       2875950.5       10306862.       2879465.5       10305893.
      2878718.75       10304076.      2879532.75       10302838.
      2886204.25       10304745.        2887938.       10303323.

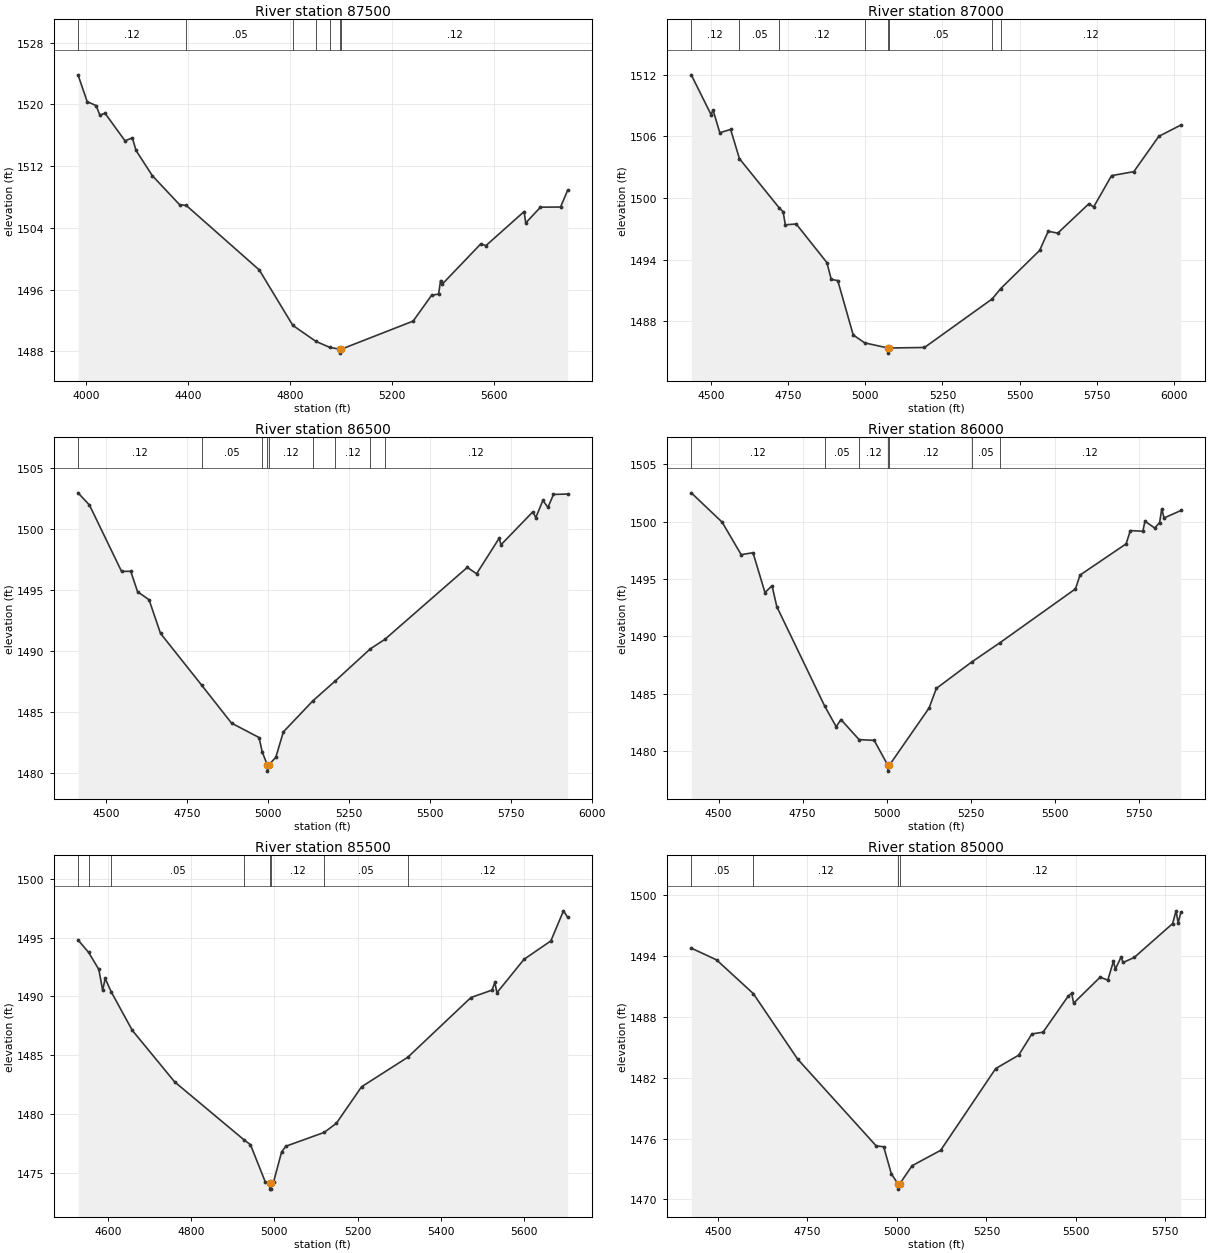
Type RM Length L Ch R = 1 ,87500   ,500,500,500
BEGIN DESCRIPTION:
FALL CREEK 175.0
END DESCRIPTION:
XS GIS Cut Line= 3
       2839405.7     10303553.12      2838608.59      10302898.6
      2837905.71     10302353.14
#Sta/Elev= 30
  3968.6 1523.84  4004.5 1520.37  4039.7 1519.85    4054 1518.64  4074.8 1518.85
    4153 1515.29  4181.7 1515.67  4196.1 1514.05  4259.9 1510.78  4366.9 1507.02
  4393.6 1506.91  4679.7 1498.56  4811.2 1491.38    4902  1489.3  4955.9 1488.53
  4996.6 1488.28  4996.9 1487.78  5000.6 1488.28  5283.3 1491.93  5355.7 1495.27
  5383.4 1495.44    5391 1497.18  5397.3 1496.71    5548 1501.91  5569.3 1501.72
  5718.7 1506.12  5725.2 1504.65  5782.9 1506.69  5861.7 1506.71  5889.7  1508.9
#Mann= 7 ,-1 , 0
  3968.6     .12       0  4393.6     .05       0  4811.2     .12       0
    4902     .05       0  4955.9     .12       0  4996.6     .07       0
  5000.6     .12       0
Bank Sta=4996.6,5000.6
XS Rating Curve= 0 ,0
Exp/Cntr=0.3,0.1

Type RM Length L Ch R = 1 ,87000   ,500,500,500
BEGIN DESCRIPTION:
FALL CREEK 174.0
END DESCRIPTION:
XS GIS Cut Line= 3
       2839455.7     10303153.12      2839077.26     10302736.41
      2838205.68     10302203.11
#Sta/Elev= 30
  4437.1    1512    4501 1508.13  4507.7 1508.56  4529.4 1506.36  4564.5 1506.68
    4593 1503.83  4722.3 1499.02  4734.3 1498.67  4741.5 1497.39  4776.7 1497.47
    4876 1493.71  4890.2 1492.07  4911.2 1491.96  4961.2 1486.66  4998.4 1485.89
  5073.7 1485.39    5074 1484.89  5077.7 1485.39  5191.8 1485.44  5410.9 1490.17
  5438.3 1491.17  5564.6  1494.9  5592.3 1496.76  5623.2 1496.58  5723.8 1499.44
  5739.3 1499.13  5797.3 1502.18  5869.4 1502.57  5950.2 1506.01  6021.8 1507.11
#Mann= 8 ,-1 , 0
  4437.1     .12       0    4593     .05       0  4722.3     .12       0
  4998.4     .05       0  5073.7     .05       0  5077.7     .05       0
  5410.9     .05       0  5438.3     .12       0
Bank Sta=5073.7,5077.7
XS Rating Curve= 0 ,0
Exp/Cntr=0.3,0.1

Type RM Length L Ch R = 1 ,86500   ,500,500,500
BEGIN DESCRIPTION:
FALL CREEK 173.0
END DESCRIPTION:
XS GIS Cut Line= 3
      2839905.65     10302853.08       2839481.2     10302448.47
      2839105.69     10301603.12
#Sta/Elev= 30
  4413.6 1502.95  4448.9 1501.95    4548 1496.52  4576.3 1496.53  4597.4 1494.86
  4632.9  1494.2  4668.2 1491.45  4795.9 1487.19  4887.4 1484.11  4972.3 1482.93
  4982.2 1481.75    4998 1480.68  4998.3 1480.18    5002 1480.68  5024.1 1481.31
  5047.4 1483.39  5138.8 1485.94    5206 1487.52  5315.6 1490.18  5360.6 1490.96
  5615.1 1496.85  5643.9 1496.33  5713.6 1499.24  5719.1  1498.7  5817.6  1501.4
  5826.5 1500.92  5848.4 1502.33  5864.1 1501.76  5881.2 1502.82    5925 1502.85
#Mann= 9 ,-1 , 0
  4413.6     .12       0  4795.9     .05       0  4982.2     .12       0
    4998     .07       0    5002     .12       0  5138.8     .05       0
    5206     .12       0  5315.6     .05       0  5360.6     .12       0
Bank Sta=4998,5002
XS Rating Curve= 0 ,0
Exp/Cntr=0.3,0.1

Type RM Length L Ch R = 1 ,86000   ,500,500,500
BEGIN DESCRIPTION:
FALL CREEK 172.0
END DESCRIPTION:
XS GIS Cut Line= 3
       2840305.7     10302603.12      2839903.56     10302182.95
       2839205.7     10301653.12
#Sta/Elev= 30
  4418.4 1502.52  4510.4 1499.96    4567 1497.13  4602.2  1497.3  4637.8 1493.83
  4658.9 1494.42    4673  1492.6  4815.3 1483.95  4849.8 1482.13  4863.9 1482.76
    4918 1481.01    4963 1480.94  5003.8 1478.76  5004.1 1478.26  5007.8 1478.76
  5126.5 1483.77    5148 1485.47  5253.2 1487.77  5336.7 1489.44  5562.3 1494.15
  5575.7 1495.35  5712.9 1498.07  5725.6 1499.23  5762.8 1499.17  5769.1 1500.05
  5798.2 1499.45  5812.8 1499.93    5819 1501.12    5826 1500.33  5876.2 1500.98
#Mann= 7 ,-1 , 0
  4418.4     .12       0  4815.3     .05       0    4918     .12       0
  5003.8     .07       0  5007.8     .12       0  5253.2     .05       0
  5336.7     .12       0
Bank Sta=5003.8,5007.8
XS Rating Curve= 0 ,0
Exp/Cntr=0.3,0.1

Type RM Length L Ch R = 1 ,85500   ,500,500,500
BEGIN DESCRIPTION:
FALL CREEK 171.0
END DESCRIPTION:
XS GIS Cut Line= 3
      2840455.68     10302203.11      2840202.93     10301804.84
      2839505.72     10301703.12
#Sta/Elev= 30
  4528.3  1494.8  4553.8 1493.74  4578.3 1492.29  4587.5 1490.51  4593.5 1491.52
  4608.1 1490.38  4658.6 1487.11  4760.4 1482.72  4926.2 1477.81  4942.6 1477.37
  4978.4 1474.18  4988.8 1474.09  4989.1 1473.59  4992.6 1473.59  4992.8 1474.09
  4998.1 1474.21  5017.4 1476.76  5027.5 1477.24  5119.8 1478.42  5148.8 1479.19
  5209.4  1482.3  5320.6 1484.82  5472.2  1489.9  5522.7 1490.53  5529.6 1491.18
  5534.7 1490.31  5599.6 1493.15  5664.2 1494.72  5694.5 1497.28  5704.6 1496.73
#Mann= 8 ,-1 , 0
  4528.3     .05       0  4553.8     .12       0  4608.1     .05       0
  4926.2     .12       0  4988.8     .07       0  4992.8     .12       0
  5119.8     .05       0  5320.6     .12       0
Bank Sta=4988.8,4992.8
XS Rating Curve= 0 ,0
Exp/Cntr=0.3,0.1

Type RM Length L Ch R = 1 ,85000   ,500,500,500
BEGIN DESCRIPTION:
FALL CREEK 170.0
END DESCRIPTION:
XS GIS Cut Line= 3
      2840905.67      10301803.1      2840486.84     10301410.02
      2839805.72     10301003.13
#Sta/Elev= 30
  4425.6  1494.8  4496.2 1493.64  4598.9 1490.31  4722.8 1483.84  4942.1 1475.28
  4963.1 1475.19  4984.6 1472.51  5003.4 1471.51  5003.7 1471.01  5007.4 1471.51
  5042.4 1473.32  5122.2 1474.84  5275.9 1482.91  5340.1 1484.23  5377.1 1486.33
  5408.2  1486.5  5478.9 1490.08    5488 1490.35  5493.8 1489.37  5567.7 1491.93
  5589.1 1491.64  5604.7 1493.48  5610.5 1492.74  5626.1 1493.92  5631.9 1493.38
  5663.1 1493.88  5770.1 1497.22  5779.8 1498.48  5785.7 1497.28  5793.4 1498.36
#Mann= 4 ,-1 , 0
  4425.6     .05       0  4598.9     .12       0  5003.4     .07       0
  5007.4     .12       0
Bank Sta=5003.4,5007.4
XS Rating Curve= 0 ,0
Exp/Cntr=0.3,0.1

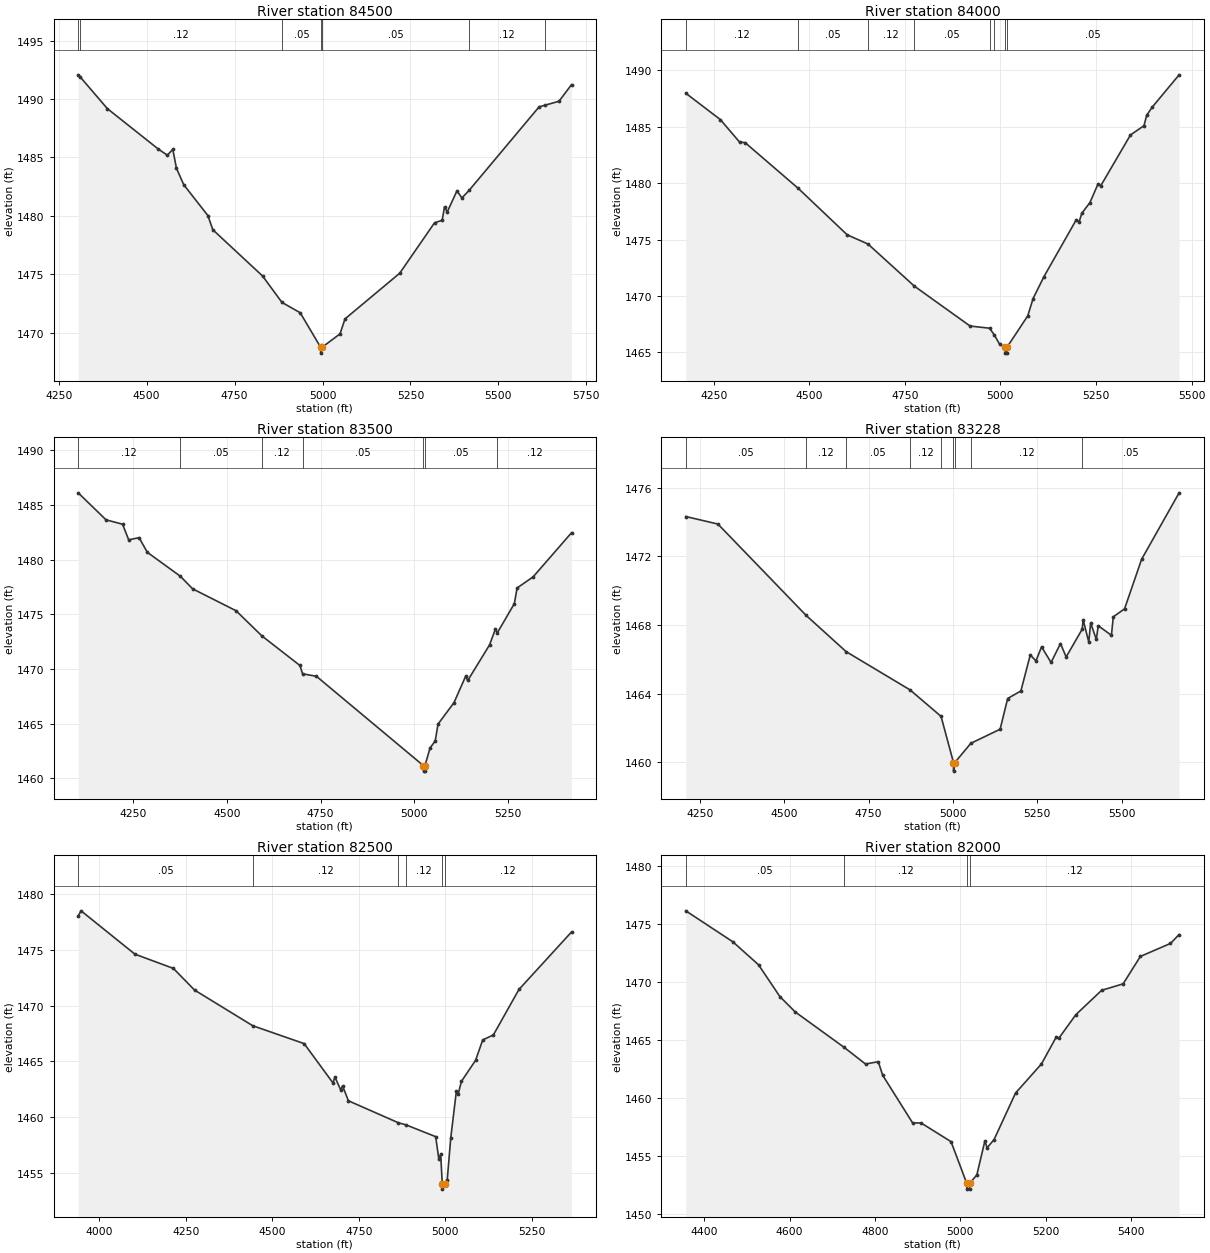
Type RM Length L Ch R = 1 ,84500   ,500,500,500
BEGIN DESCRIPTION:
FALL CREEK 169.0
END DESCRIPTION:
XS GIS Cut Line= 3
      2840905.68     10301653.11      2840727.46     10300981.66
      2840205.68     10300503.11
#Sta/Elev= 30
  4305.3 1492.07  4310.7  1491.9  4388.1 1489.18  4532.9 1485.72  4558.7 1485.19
  4574.3 1485.69  4584.6 1484.08  4605.3 1482.67  4674.1 1480.02  4688.1 1478.81
  4829.6 1474.85  4884.7 1472.59  4936.4 1471.71  4994.7 1468.75  4994.9 1468.25
  4998.7 1468.75  5049.8  1469.9  5063.9 1471.18  5219.5 1475.09  5318.6 1479.41
  5340.2 1479.62    5347 1480.78  5354.4 1480.32  5382.3 1482.14  5396.3 1481.53
  5416.5 1482.17  5615.8 1489.33    5634 1489.48  5672.5 1489.81    5708 1491.23
#Mann= 7 ,-1 , 0
  4305.3     .05       0  4310.7     .12       0  4884.7     .05       0
  4994.7     .05       0  4998.7     .05       0  5416.5     .12       0
    5634     .05       0
Bank Sta=4994.7,4998.7
XS Rating Curve= 0 ,0
Exp/Cntr=0.3,0.1

Type RM Length L Ch R = 1 ,84000   ,500,500,500
BEGIN DESCRIPTION:
FALL CREEK 168.0
END DESCRIPTION:
XS GIS Cut Line= 3
      2841005.69     10301453.09      2841085.54     10300634.18
      2840755.71     10300303.14
#Sta/Elev= 30
  4177.2 1487.97  4267.6 1485.63  4317.8 1483.64  4332.3 1483.59  4470.8 1479.55
  4599.2 1475.42  4653.7  1474.6  4774.9 1470.87  4920.7 1467.33  4971.5 1467.14
    4984 1466.55    4998 1465.71  5012.8 1465.43  5013.1 1464.93  5016.6 1464.93
  5016.8 1465.43  5071.4 1468.23  5085.5 1469.77  5113.8 1471.71  5198.7 1476.77
  5205.7 1476.55  5212.8 1477.33    5234 1478.27  5255.2 1479.92  5262.3 1479.76
  5340.1 1484.27  5375.4 1485.09  5382.5 1486.01  5396.6 1486.72  5467.3  1489.6
#Mann= 8 ,-1 , 0
  4177.2     .12       0  4470.8     .05       0  4653.7     .12       0
  4774.9     .05       0  4971.5     .12       0    4984     .05       0
  5012.8     .05       0  5016.8     .05       0
Bank Sta=5012.8,5016.8
XS Rating Curve= 0 ,0
Exp/Cntr=0.3,0.1

Type RM Length L Ch R = 1 ,83500   ,272,272,272
BEGIN DESCRIPTION:
FALL CREEK 167.0
END DESCRIPTION:
XS GIS Cut Line= 3
      2841155.68     10301403.12      2841574.39     10300610.63
      2841355.69     10300253.12
#Sta/Elev= 30
  4103.7  1486.1  4177.9 1483.63    4222 1483.23  4238.3  1481.8    4266    1482
    4288 1480.66  4376.1 1478.47  4408.8 1477.32  4524.5 1475.32  4593.4 1473.02
  4694.9 1470.31    4702 1469.55    4739 1469.32  5024.3 1461.15  5024.6 1460.65
  5028.1 1460.65  5028.3 1461.15  5041.8 1462.76  5055.7 1463.41  5063.1 1464.95
  5105.7 1466.91  5136.6 1469.31  5142.4 1468.94  5200.5 1472.19  5215.9 1473.61
  5221.7 1473.32  5266.7 1475.97    5274  1477.4  5316.6 1478.41  5419.1 1482.45
#Mann= 7 ,-1 , 0
  4103.7     .12       0  4376.1     .05       0  4593.4     .12       0
    4702     .05       0  5024.3     .05       0  5028.3     .05       0
  5221.7     .12       0
Bank Sta=5024.3,5028.3
XS Rating Curve= 0 ,0
Exp/Cntr=0.3,0.1

Type RM Length L Ch R = 1 ,83228   ,728,728,728
BEGIN DESCRIPTION:
Mapping XS dcf22592
END DESCRIPTION:
XS GIS Cut Line= 4
      2841712.59     10301437.34      2841816.75     10300873.14
      2841851.47     10300569.33      2841591.07     10300048.53
#Sta/Elev= 30
  4208.4 1474.31  4303.6 1473.87    4565 1468.55  4683.5 1466.44    4873 1464.21
  4964.8 1462.67  5001.6 1459.98  5001.8 1459.48  5005.6 1459.98    5053  1461.1
  5139.8 1461.92  5162.2 1463.71  5201.3 1464.15  5229.2 1466.25    5246  1465.9
  5262.6 1466.72  5290.7 1465.81  5318.7 1466.91  5335.5 1466.13  5383.1 1467.75
  5385.8  1468.3  5402.5    1467  5408.1 1468.11  5424.9 1467.15  5430.5 1467.95
  5469.6 1467.39  5475.2 1468.47  5508.5 1468.93  5559.1 1471.82  5670.2 1475.69
#Mann= 9 ,-1 , 0
  4208.4     .05       0    4565     .12       0  4683.5     .05       0
    4873     .12       0  4964.8     .05       0  5001.6     .05       0
  5005.6     .05       0    5053     .12       0  5383.1     .05       0
Bank Sta=5001.6,5005.6
XS Rating Curve= 0 ,0
Exp/Cntr=0.3,0.1

Type RM Length L Ch R = 1 ,82500   ,500,500,500
BEGIN DESCRIPTION:
FALL CREEK 165.0
END DESCRIPTION:
XS GIS Cut Line= 3
       2842755.7     10301203.14      2842273.36       10300258.
      2842355.68     10299903.12
#Sta/Elev= 30
  3938.9 1478.07  3947.2 1478.52  4102.8 1474.63    4214 1473.35    4275 1471.41
    4443 1468.21  4591.8  1466.6  4675.1 1463.07  4680.7  1463.6  4697.3 1462.45
  4702.9  1462.8  4719.6 1461.47  4863.7  1459.5  4885.8 1459.31  4971.8 1458.25
  4980.7 1456.28  4986.3 1456.65  4990.8 1454.04  4991.3 1453.54  4997.8 1454.04
  5005.1 1454.34  5015.3 1458.11  5031.5 1462.31  5036.7 1462.05  5046.1 1463.21
  5087.1  1465.1  5107.7 1466.93  5138.5 1467.38  5212.4 1471.46  5364.3 1476.62
#Mann= 6 ,-1 , 0
  3938.9     .05       0    4443     .12       0  4863.7     .05       0
  4885.8     .12       0  4990.8     .07       0  4997.8     .12       0
Bank Sta=4990.8,4997.8
XS Rating Curve= 0 ,0
Exp/Cntr=0.3,0.1

Type RM Length L Ch R = 1 ,82000   ,500,500,500
BEGIN DESCRIPTION:
FALL CREEK 164.0
END DESCRIPTION:
XS GIS Cut Line= 3
      2842755.68     10301103.08      2842718.15     10300461.38
      2842655.68      10299953.1
#Sta/Elev= 30
  4357.2 1476.14  4467.4 1473.47  4527.5 1471.49  4577.5 1468.75  4613.3 1467.43
  4727.7 1464.38  4777.9 1462.94  4807.9 1463.14    4818 1461.98  4888.1 1457.87
  4908.1 1457.86  4978.2 1456.25  5014.9 1452.66  5015.4 1452.16  5021.4 1452.16
  5021.9 1452.66  5038.6 1453.39  5057.4 1456.32  5062.5 1455.72  5078.9 1456.43
  5129.2 1460.44  5189.7 1462.94    5225  1465.3  5230.1 1465.14  5270.3 1467.19
  5330.7 1469.29  5381.1 1469.85  5421.4 1472.21  5491.9 1473.33  5512.1  1474.1
#Mann= 4 ,-1 , 0
  4357.2     .05       0  4727.7     .12       0  5014.9     .07       0
  5021.9     .12       0
Bank Sta=5014.9,5021.9
XS Rating Curve= 0 ,0
Exp/Cntr=0.3,0.1

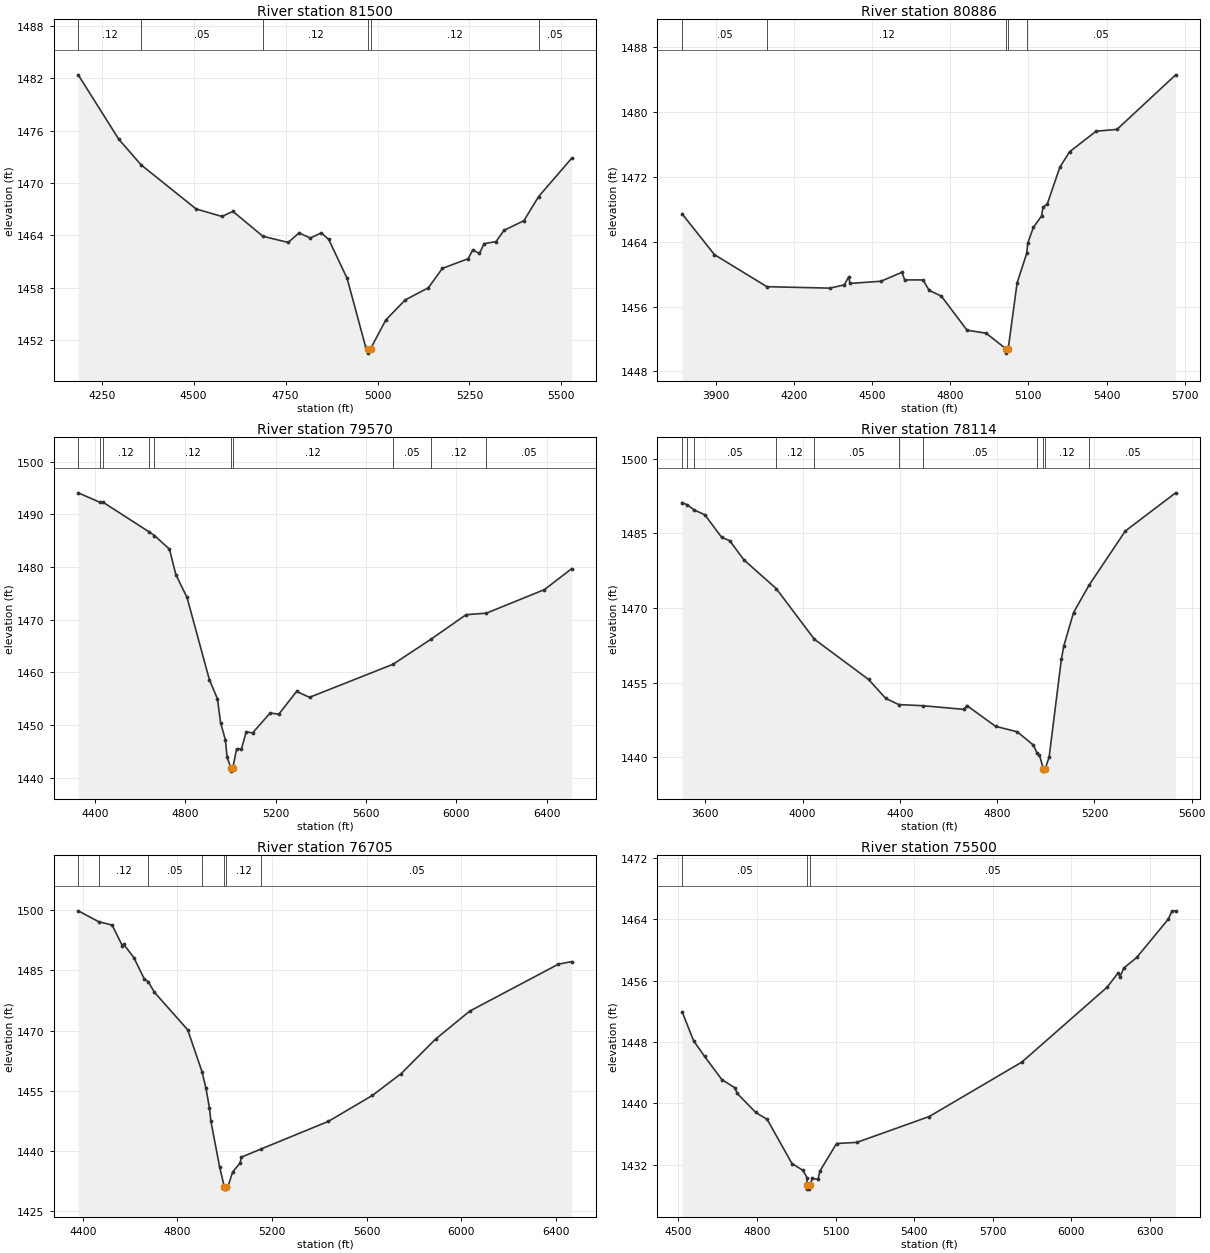
Type RM Length L Ch R = 1 ,81500   ,614,614,614
BEGIN DESCRIPTION:
FALL CREEK 163.0
END DESCRIPTION:
XS GIS Cut Line= 3
      2843155.69     10301153.13      2843108.57     10300340.59
      2842905.69     10299853.13
#Sta/Elev= 30
  4186.1 1482.39  4296.3 1475.01    4357 1472.07  4506.7 1467.01  4576.8 1466.15
  4606.8 1466.73  4688.2 1463.88  4757.1 1463.17  4786.4 1464.26  4817.2 1463.68
  4847.2 1464.27  4867.3 1463.51  4917.3 1459.05    4968 1451.13  4973.9 1450.98
  4974.4 1450.48    4981 1450.98  5022.4 1454.28  5075.5 1456.59  5138.1 1457.97
  5176.3  1460.2  5246.4 1461.31  5258.7  1462.3  5277.1 1461.92  5289.7 1463.03
  5322.2 1463.27  5343.9 1464.56    5398 1465.67  5437.9 1468.43    5528 1472.83
#Mann= 6 ,-1 , 0
  4186.1     .12       0    4357     .05       0  4688.2     .12       0
  4973.9     .07       0    4981     .12       0  5437.9     .05       0
Bank Sta=4973.9,4981
XS Rating Curve= 0 ,0
Exp/Cntr=0.3,0.1

Type RM Length L Ch R = 1 ,80886   ,1316,1316,1316
BEGIN DESCRIPTION:
Mapping XS 2139a24a
END DESCRIPTION:
XS GIS Cut Line= 5
      2843587.58     10301059.77      2843492.09     10300360.99
      2843444.35     10299996.41      2843405.29     10299749.01
      2842910.55     10299462.59
#Sta/Elev= 30
  3770.3 1467.44  3894.1 1462.42  4095.5 1458.46  4337.7 1458.28  4392.7 1458.68
    4410 1459.67    4415 1458.86  4533.9 1459.13  4614.6 1460.24  4624.7  1459.3
  4695.3 1459.29    4719    1458  4765.9 1457.29  4864.3 1453.09  4937.7 1452.72
  5015.1 1450.76  5015.6 1450.26  5022.3 1450.76  5056.6 1458.93  5093.7 1462.59
  5097.3 1463.81  5118.8 1465.77  5150.3 1467.17  5156.1 1468.28  5171.9 1468.62
  5220.7  1473.2    5258  1475.1  5359.9 1477.64  5440.3 1477.87  5665.4  1484.6
#Mann= 5 ,-1 , 0
  3770.3     .05       0  4095.5     .12       0  5015.1     .07       0
  5022.3     .12       0  5093.7     .05       0
Bank Sta=5015.1,5022.3
XS Rating Curve= 0 ,0
Exp/Cntr=0.3,0.1

Type RM Length L Ch R = 1 ,79570   ,1456,1456,1456
BEGIN DESCRIPTION:
Mapping XS 8e7bfd56
END DESCRIPTION:
XS GIS Cut Line= 5
      2844472.99     10300894.84      2844308.07     10300508.56
      2843995.57     10300165.68      2843730.81     10299692.59
      2843092.81     10299280.28
#Sta/Elev= 30
  4325.2 1494.07    4421 1492.28  4434.2 1492.31  4639.3 1486.66  4662.7 1485.97
  4729.4 1483.38  4757.8 1478.52  4807.1 1474.22  4906.4 1458.57    4942 1454.97
  4955.7 1450.44  4977.3 1447.17  4984.1    1444    5002 1441.77  5002.5 1441.27
  5009.4 1441.77  5026.7 1445.51  5048.3 1445.49  5069.2 1448.72  5097.6 1448.52
  5175.3  1452.3  5213.5 1452.07  5292.3 1456.39  5349.6 1455.27  5719.9 1461.55
  5888.2 1466.32  6043.1 1470.95  6133.1 1471.24  6390.1 1475.71  6510.9 1479.69
#Mann= 10 ,-1 , 0
  4325.2     .12       0    4421     .05       0  4434.2     .12       0
  4639.3     .05       0  4662.7     .12       0    5002     .07       0
  5009.4     .12       0  5719.9     .05       0  5888.2     .12       0
  6133.1     .05       0
Bank Sta=5002,5009.4
XS Rating Curve= 0 ,0
Exp/Cntr=0.3,0.1

Type RM Length L Ch R = 1 ,78114   ,1409,1409,1409
BEGIN DESCRIPTION:
Mapping XS 500ade63
END DESCRIPTION:
XS GIS Cut Line= 5
      2844676.99     10300604.04       2844538.1     10299987.73
       2844494.7     10299536.34      2844542.44     10298876.62
      2844616.22     10298603.19
#Sta/Elev= 30
  3504.3 1491.22  3523.8  1490.8  3554.8 1489.71  3597.5 1488.77  3666.8 1484.23
    3700 1483.54  3758.4 1479.69  3891.2 1473.91  4048.2 1463.71  4271.3 1455.61
  4341.6  1451.8    4396 1450.55  4495.1 1450.33    4663 1449.59  4675.2 1450.37
  4793.3 1446.19  4883.5 1445.06  4949.1 1442.39  4964.5 1440.75  4973.8 1440.43
  4989.8 1437.66  4990.3 1437.16  4997.9 1437.66  5013.9 1440.02    5064 1459.63
    5074 1462.32  5114.1 1469.07  5177.7 1474.57  5327.1 1485.49  5534.2 1493.18
#Mann= 11 ,-1 , 0
  3504.3     .05       0  3523.8     .12       0  3554.8     .05       0
  3891.2     .12       0  4048.2     .05       0    4396     .12       0
  4495.1     .05       0  4964.5     .12       0  4989.8     .07       0
  4997.9     .12       0  5177.7     .05       0
Bank Sta=4989.8,4997.9
XS Rating Curve= 0 ,0
Exp/Cntr=0.3,0.1

Type RM Length L Ch R = 1 ,76705   ,1205,1205,1205
BEGIN DESCRIPTION:
Mapping XS 9b55ba68
END DESCRIPTION:
XS GIS Cut Line= 4
      2845249.91     10300729.91      2845414.84     10299992.07
      2845267.27     10299471.23       2844872.3     10298789.81
#Sta/Elev= 30
    4381 1499.82  4467.7 1497.11  4524.2 1496.28  4567.6 1491.11  4572.7 1491.54
  4616.1 1488.16  4659.6 1482.93  4677.3 1482.13    4703 1479.53  4843.5  1470.2
  4904.1 1459.74  4920.8 1455.61  4935.4 1450.75  4941.3  1447.5  4978.8 1435.93
  4998.6 1431.02  4999.1 1430.52  5006.9 1431.02    5013 1431.02  5033.5 1434.82
  5064.3 1436.98  5070.8 1438.49  5153.3 1440.51  5437.4 1447.38  5624.2 1453.87
  5745.6  1459.3  5890.5 1467.87  6035.4 1474.86  6409.8 1486.54    6466 1487.17
#Mann= 7 ,-1 , 0
    4381     .05       0  4467.7     .12       0  4677.3     .05       0
  4904.1     .12       0  4998.6     .07       0  5006.9     .12       0
  5153.3     .05       0
Bank Sta=4998.6,5006.9
XS Rating Curve= 0 ,0
Exp/Cntr=0.3,0.1

Type RM Length L Ch R = 1 ,75500   ,500,500,500
BEGIN DESCRIPTION:
FALL CREEK 151.0
END DESCRIPTION:
XS GIS Cut Line= 3
       2846755.7     10300103.14      2846486.18     10299699.32
      2845505.68      10298703.1
#Sta/Elev= 30
  4514.5 1451.97  4558.1 1448.19  4600.2 1446.14  4666.2 1443.11  4717.3 1442.02
  4723.3 1441.36  4795.4 1438.83  4839.2 1437.92  4933.6 1432.17  4975.6 1431.28
  4990.7 1430.34  4991.3 1429.33  4991.8 1428.83  5000.1 1428.83  5000.6 1429.33
  5011.8 1430.22  5033.1 1430.11  5040.1 1431.18  5103.8 1434.78  5181.5 1434.93
  5457.4  1438.3  5810.8  1445.4  6136.1 1455.16  6178.6 1457.06  6185.7 1456.54
  6199.8 1457.66  6249.3 1459.05  6369.6 1464.04  6383.7  1465.1  6397.8 1465.13
#Mann= 3 ,-1 , 0
  4514.5     .05       0  4991.3     .05       0  5000.6     .05       0
Bank Sta=4991.3,5000.6
XS Rating Curve= 0 ,0
Exp/Cntr=0.3,0.1

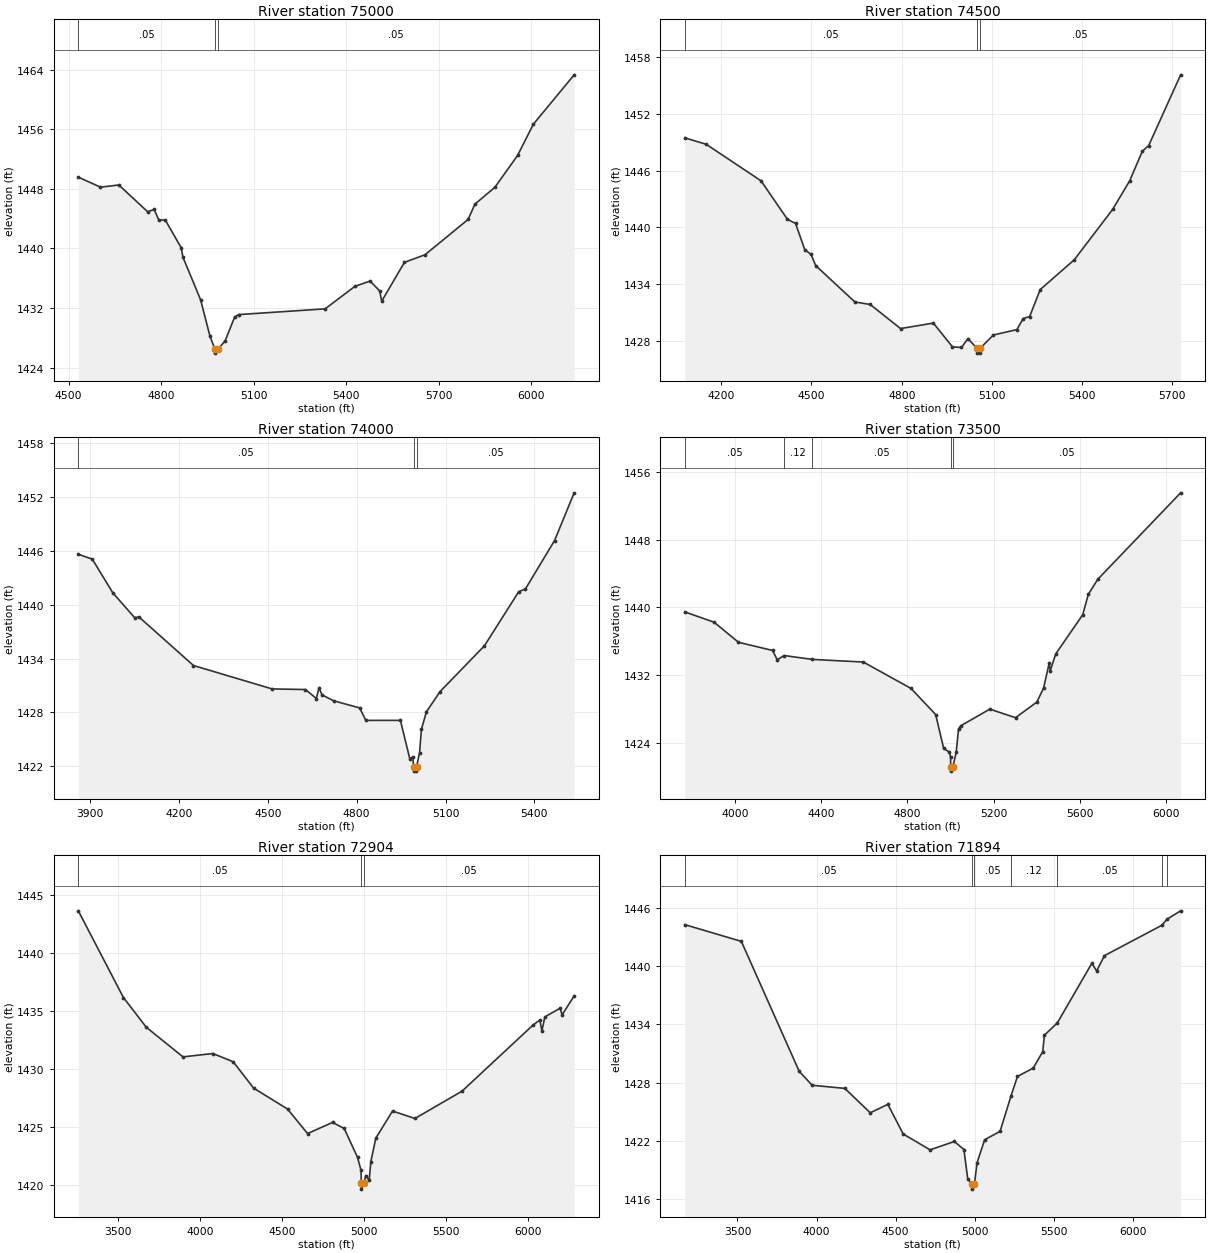
Type RM Length L Ch R = 1 ,75000   ,500,500,500
BEGIN DESCRIPTION:
FALL CREEK 150.0
END DESCRIPTION:
XS GIS Cut Line= 3
      2847155.69     10299553.12      2846763.73     10299297.05
      2846205.67     10298303.09
#Sta/Elev= 30
  4531.8 1449.56  4603.5 1448.22  4663.1 1448.51  4756.6 1444.92  4777.7 1445.23
  4792.8  1443.8  4813.9  1443.8  4865.2 1440.11  4871.2 1438.81  4928.4  1433.1
  4958.7 1428.22  4975.1 1426.45  4975.6 1425.95  4984.5 1426.45  5008.2 1427.62
  5038.9  1430.8  5051.6 1431.12  5332.2 1431.89  5428.8 1434.91  5478.2 1435.62
  5509.1  1434.3  5515.9 1432.93  5589.4 1438.13  5656.2 1439.15  5795.8 1443.88
  5818.1 1445.94  5883.2 1448.22  5956.4 1452.47  6007.5 1456.66  6139.9 1463.29
#Mann= 3 ,-1 , 0
  4531.8     .05       0  4975.1     .05       0  4984.5     .05       0
Bank Sta=4975.1,4984.5
XS Rating Curve= 0 ,0
Exp/Cntr=0.3,0.1

Type RM Length L Ch R = 1 ,74500   ,500,500,500
BEGIN DESCRIPTION:
FALL CREEK 149.0
END DESCRIPTION:
XS GIS Cut Line= 3
       2847355.7     10299603.14      2846861.29     10298825.98
      2846355.71     10298303.14
#Sta/Elev= 30
  4078.9 1449.46  4150.1 1448.78  4332.1 1444.92  4420.2 1440.84  4447.2  1440.4
  4477.7 1437.63  4498.9 1437.12  4514.1 1435.94  4644.5 1432.09  4695.2 1431.83
  4796.1 1429.28  4905.3 1429.86  4968.8 1427.34  4998.7 1427.28  5020.1 1428.21
  5050.8 1427.18  5051.3 1426.68  5059.8 1426.68  5060.3 1427.18  5104.9  1428.6
  5182.9 1429.17    5204 1430.34  5225.3 1430.55  5260.6 1433.41  5373.8 1436.56
  5501.1 1441.88  5557.7  1444.9  5600.1 1448.05  5621.2 1448.65  5727.3 1456.13
#Mann= 3 ,-1 , 0
  4078.9     .05       0  5050.8     .05       0  5060.3     .05       0
Bank Sta=5050.8,5060.3
XS Rating Curve= 0 ,0
Exp/Cntr=0.3,0.1

Type RM Length L Ch R = 1 ,74000   ,500,500,500
BEGIN DESCRIPTION:
FALL CREEK 148.0
END DESCRIPTION:
XS GIS Cut Line= 3
      2847355.69     10299453.13       2846992.5     10298372.96
      2846505.65     10298153.09
#Sta/Elev= 30
  3860.4 1445.63  3907.7 1445.08  3976.5 1441.34  4050.3 1438.56  4065.3 1438.63
  4249.1 1433.22  4514.5 1430.61  4627.2 1430.54    4664 1429.54  4672.8 1430.74
  4683.3 1429.94  4721.8 1429.29  4809.9 1428.49    4831  1427.1  4947.7  1427.1
  4979.2 1422.84  4989.3 1422.99  4992.3 1421.94  4992.8 1421.44  5001.8 1421.44
  5002.3 1421.94  5012.4 1423.51  5018.5  1426.1  5035.5 1428.06  5081.7 1430.32
  5231.4 1435.42    5347 1441.45  5369.6 1441.76  5468.1 1447.16  5534.2 1452.48
#Mann= 3 ,-1 , 0
  3860.4     .05       0  4992.3     .05       0  5002.3     .05       0
Bank Sta=4992.3,5002.3
XS Rating Curve= 0 ,0
Exp/Cntr=0.3,0.1

Type RM Length L Ch R = 1 ,73500   ,596,596,596
BEGIN DESCRIPTION:
FALL CREEK 147.0
END DESCRIPTION:
XS GIS Cut Line= 3
      2847782.02     10299289.81      2847400.55     10298118.25
      2846393.18     10297768.99
#Sta/Elev= 30
  3767.9 1439.47  3903.9 1438.25  4016.8 1435.88  4174.6 1434.92  4196.5 1433.81
  4228.2 1434.32  4359.1 1433.86  4595.3 1433.55  4816.1 1430.44  4930.7 1427.35
  4967.9 1423.35  4994.6 1422.92  4999.8  1422.3  5000.4 1421.17  5000.9 1420.67
  5010.4 1421.17    5026  1422.9  5036.9 1425.68  5047.5 1426.03  5181.7 1427.99
    5301 1426.98  5399.7 1428.82  5430.8 1430.47  5456.7 1433.39  5461.9 1432.54
  5487.8 1434.53  5612.4 1439.13  5638.2 1441.54  5682.5 1443.33  6066.2 1453.53
#Mann= 5 ,-1 , 0
  3767.9     .05       0  4228.2     .12       0  4359.1     .05       0
  5000.4     .05       0  5010.4     .05       0
Bank Sta=5000.4,5010.4
XS Rating Curve= 0 ,0
Exp/Cntr=0.3,0.1

Type RM Length L Ch R = 1 ,72904   ,1010,1010,1010
BEGIN DESCRIPTION:
Mapping XS 25fbee53
END DESCRIPTION:
XS GIS Cut Line= 4
      2847976.47     10299345.38      2847844.52      10298366.2
      2847691.75     10297477.31      2847969.53     10296380.08
#Sta/Elev= 30
  3259.2 1443.62  3533.9 1436.16  3673.5  1433.6  3896.9 1431.05  4078.8 1431.34
    4203 1430.63  4327.7 1428.36  4534.5 1426.56  4656.2 1424.45  4808.4 1425.41
  4879.5 1424.89  4960.6 1422.41  4982.2 1421.28  4983.8 1420.17  4984.3 1419.67
  4998.3 1420.17  5011.4 1420.83  5031.7 1420.43  5042.1 1422.04  5072.2 1424.06
  5174.1 1426.39  5310.6 1425.75  5597.6  1428.1  6030.3 1433.79  6071.6 1434.22
  6084.5 1433.29  6102.5 1434.49  6195.3 1435.24  6207.5 1434.67    6281  1436.3
#Mann= 3 ,-1 , 0
  3259.2     .05       0  4983.8     .05       0  4998.3     .05       0
Bank Sta=4983.8,4998.3
XS Rating Curve= 0 ,0
Exp/Cntr=0.3,0.1

Type RM Length L Ch R = 1 ,71894   ,1038,1038,1038
BEGIN DESCRIPTION:
Mapping XS ae7ad4d5
END DESCRIPTION:
XS GIS Cut Line= 4
      2848094.52     10299748.16       2848247.3     10298477.31
      2848504.25     10297845.37      2848552.86     10296671.76
#Sta/Elev= 30
  3166.7 1444.24  3524.3 1442.52  3890.3 1429.16  3972.4 1427.72    4179  1427.4
  4340.1 1424.89  4451.2 1425.76  4548.4 1422.71  4718.4 1421.08  4872.2 1421.94
  4932.6 1421.11  4956.7 1418.09  4984.1 1417.54  4984.6 1417.04  4998.9 1417.54
  5015.6 1419.75  5063.7 1422.12  5161.2 1422.98  5230.2 1426.61  5271.3 1428.63
  5371.3 1429.49  5431.4 1431.19  5441.4 1432.87    5523 1434.12  5741.7 1440.26
  5772.2 1439.48  5821.7 1441.05  6185.4 1444.18  6216.6 1444.79  6303.5 1445.66
#Mann= 7 ,-1 , 0
  3166.7     .05       0  4984.1     .05       0  4998.9     .05       0
  5230.2     .12       0    5523     .05       0  6185.4     .12       0
  6216.6     .05       0
Bank Sta=4984.1,4998.9
XS Rating Curve= 0 ,0
Exp/Cntr=0.3,0.1

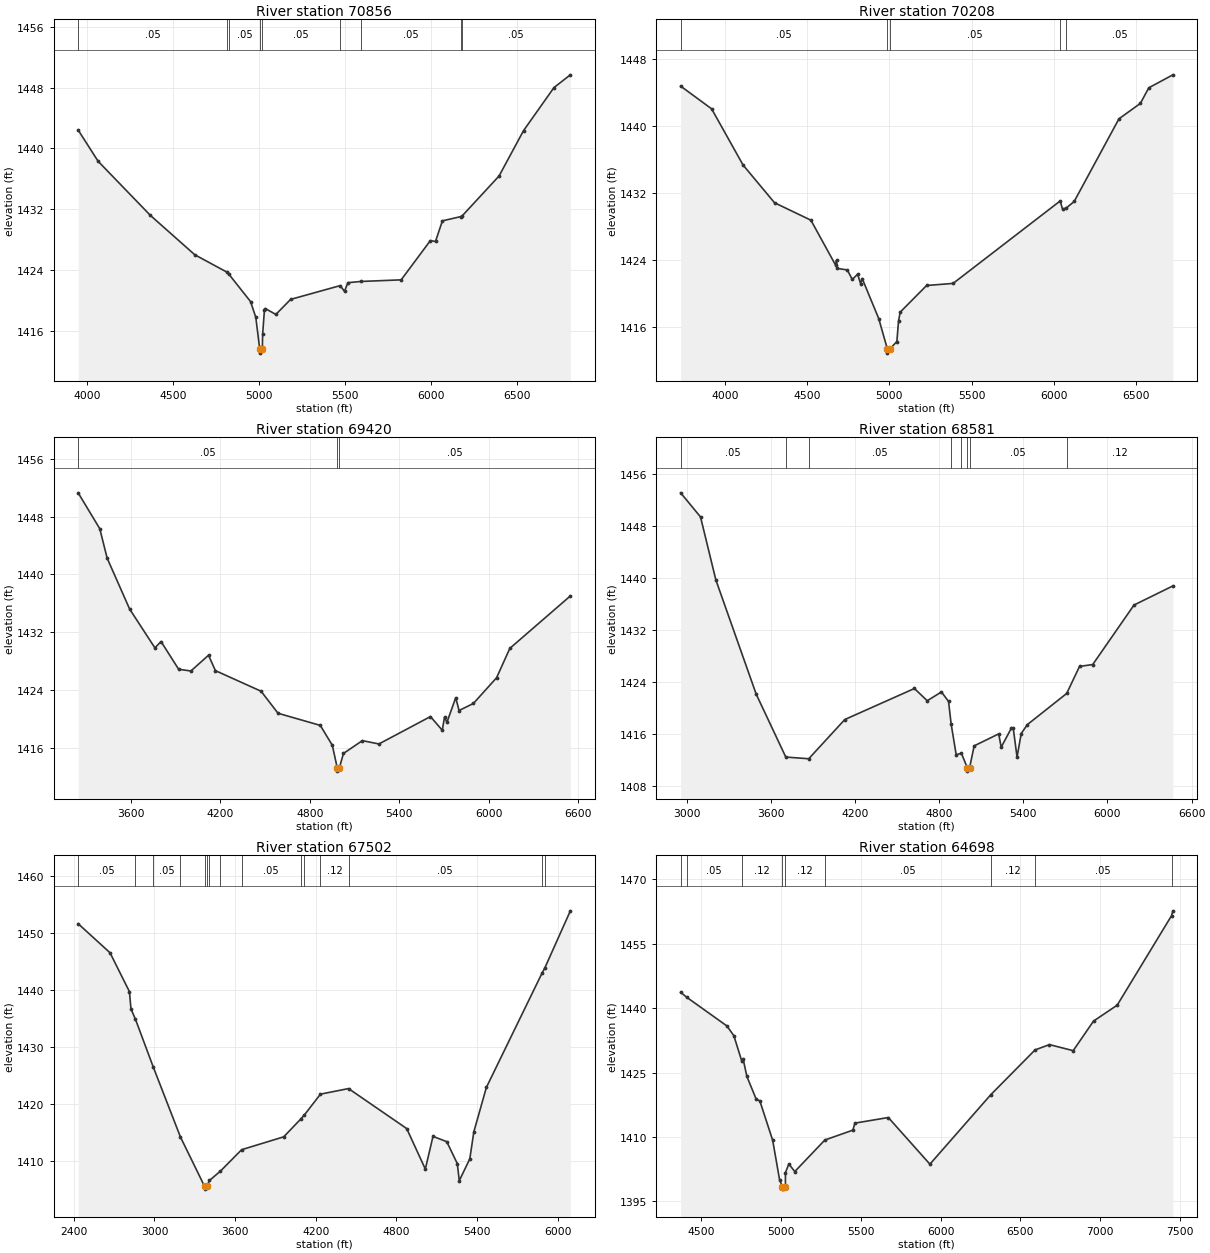
Type RM Length L Ch R = 1 ,70856   ,648,648,648
BEGIN DESCRIPTION:
Mapping XS 12f4ace4
END DESCRIPTION:
XS GIS Cut Line= 3
      2848455.65     10299852.28      2848920.91     10298581.48
      2848969.52     10297067.85
#Sta/Elev= 30
  3945.6 1442.43  4061.9 1438.32  4366.4  1431.2  4625.1 1426.02  4812.9 1423.73
  4824.9 1423.43  4950.1 1419.86  4980.6 1417.79  5003.7 1413.58  5004.2 1413.08
  5018.7 1413.58  5020.3 1415.54  5030.9 1418.75  5036.4 1418.94  5097.4 1418.17
  5183.6 1420.15  5471.9 1421.96  5497.4 1421.21  5517.4 1422.35    5595 1422.51
  5827.5 1422.72  5997.6 1427.88  6027.6 1427.77  6067.7 1430.48  6176.8 1431.05
    6182 1431.11  6397.8 1436.38  6540.5 1442.35    6718 1448.02  6813.3 1449.69
#Mann= 9 ,-1 , 0
  3945.6     .05       0  4812.9     .12       0  4824.9     .05       0
  5003.7     .05       0  5018.7     .05       0  5471.9     .12       0
    5595     .05       0  6176.8     .12       0    6182     .05       0
Bank Sta=5003.7,5018.7
XS Rating Curve= 0 ,0
Exp/Cntr=0.3,0.1

Type RM Length L Ch R = 1 ,70208   ,788,788,788
BEGIN DESCRIPTION:
Mapping XS 950c9239
END DESCRIPTION:
XS GIS Cut Line= 4
      2849316.74     10299970.41       2849434.8     10298900.92
      2849393.14     10298435.64      2849205.63     10296998.14
#Sta/Elev= 30
  3730.5 1444.76  3918.9 1442.04  4110.1 1435.32  4301.2 1430.81  4522.6 1428.72
  4673.1 1423.33  4678.2 1423.93  4683.6 1422.95  4743.9 1422.77  4774.1 1421.63
  4806.5 1422.26  4824.4 1421.14  4834.4 1421.74  4934.8 1416.96  4987.4 1413.32
  4987.9 1412.82  5002.6 1413.32  5045.2 1414.21  5055.3 1416.64  5065.3 1417.72
    5226 1420.91  5387.1 1421.16  6038.1 1431.02  6052.7 1430.04  6075.3 1430.18
  6123.3 1430.96  6395.6 1440.85  6525.6 1442.69  6577.1 1444.56  6723.3 1446.11
#Mann= 5 ,-1 , 0
  3730.5     .05       0  4987.4     .03       0  5002.6     .05       0
  6038.1     .12       0  6075.3     .05       0
Bank Sta=4987.4,5002.6
XS Rating Curve= 0 ,0
Exp/Cntr=0.3,0.1

Type RM Length L Ch R = 1 ,69420   ,839,839,839
BEGIN DESCRIPTION:
Mapping XS 1a76caf5
END DESCRIPTION:
XS GIS Cut Line= 4
      2849795.92     10300081.43      2850136.19     10298734.26
       2850059.8     10298088.42      2849483.41     10296970.37
#Sta/Elev= 30
  3248.3 1451.28  3393.2 1446.31  3442.5 1442.24  3593.3 1435.19  3762.6 1429.82
  3803.6  1430.7  3921.6 1426.86  4003.7 1426.62  4121.7  1428.8  4167.9 1426.67
  4473.9 1423.82  4587.4 1420.77  4870.5 1419.09  4951.1 1416.34  4983.7 1413.26
  4984.2 1412.76    4999 1413.26  5025.9 1415.21  5152.5 1416.98  5263.3 1416.52
  5608.5 1420.31  5687.9 1418.42  5702.8 1420.23  5719.3 1419.53  5777.9 1422.92
  5800.4 1421.15  5896.6 1422.13  6051.8 1425.69  6140.4 1429.75    6546 1437.01
#Mann= 3 ,-1 , 0
  3248.3     .05       0  4983.7     .05       0    4999     .05       0
Bank Sta=4983.7,4999
XS Rating Curve= 0 ,0
Exp/Cntr=0.3,0.1

Type RM Length L Ch R = 1 ,68581   ,1079,1079,1079
BEGIN DESCRIPTION:
Mapping XS 88e2ba78
END DESCRIPTION:
XS GIS Cut Line= 4
      2850038.96     10300137.05      2850733.41     10298880.09
       2850872.3      10298053.7      2851587.08     10297047.45
#Sta/Elev= 30
  2957.7 1453.07  3099.3 1449.37  3208.6  1439.7  3496.2 1422.15  3707.2 1412.49
  3870.7 1412.23  4127.5 1418.25  4623.9 1423.02  4715.2 1421.14  4816.6 1422.49
  4867.3 1421.03  4885.6 1417.58  4921.7 1412.85  4958.6 1413.07  5001.4 1410.83
  5001.9 1410.33    5017 1410.83  5049.8 1414.21  5224.6 1416.05  5242.4    1414
  5313.7 1416.88  5328.5  1416.9  5355.5 1412.48  5385.1  1416.1  5428.7 1417.47
  5709.3 1422.26  5800.8 1426.41  5894.8  1426.7  6189.2 1435.84    6466 1438.77
#Mann= 8 ,-1 , 0
  2957.7     .05       0  3707.2     .12       0  3870.7     .05       0
  4885.6     .12       0  4958.6     .05       0  5001.4     .05       0
    5017     .05       0  5709.3     .12       0
Bank Sta=5001.4,5017
XS Rating Curve= 0 ,0
Exp/Cntr=0.3,0.1

Type RM Length L Ch R = 1 ,67502   ,2804,2804,2804
BEGIN DESCRIPTION:
Mapping XS 609246fc
END DESCRIPTION:
XS GIS Cut Line= 4
      2850261.19     10300366.21      2850795.91     10299268.98
      2851275.08     10298734.26      2852711.65     10297783.48
#Sta/Elev= 30
  2432.6  1451.7  2669.7  1446.6  2814.1 1439.77  2825.4 1436.75  2859.1 1434.91
  2991.7 1426.52  3193.5 1414.26  3372.7 1405.61  3373.2 1405.11  3390.5 1405.61
  3409.4 1406.63  3491.3 1408.28  3648.6 1412.03  3961.6 1414.29  4089.9 1417.45
  4113.3 1418.07    4235 1421.78  4443.9 1422.76  4876.6 1415.74    5015 1408.63
  5072.1 1414.37  5174.5 1413.44  5252.7  1409.6  5267.7 1406.59  5345.9 1410.43
    5376 1415.18  5469.3 1422.97  5883.1 1443.02  5902.8 1443.88  6093.9 1453.96
#Mann= 15 ,-1 , 0
  2432.6     .05       0  2859.1     .12       0  2991.7     .05       0
  3193.5     .12       0  3372.7     .05       0  3390.5     .12       0
  3409.4     .05       0  3491.3     .12       0  3648.6     .05       0
  4089.9     .12       0  4113.3     .05       0    4235     .12       0
  4443.9     .05       0  5883.1     .12       0  5902.8     .05       0
Bank Sta=3372.7,3390.5
XS Rating Curve= 0 ,0
Exp/Cntr=0.3,0.1

Type RM Length L Ch R = 1 ,64698   ,600,600,600
BEGIN DESCRIPTION:
Mapping XS 85cb1437
END DESCRIPTION:
XS GIS Cut Line= 4
      2850448.69     10300574.53      2851316.75     10300060.64
      2852129.25     10299512.03      2852920.81     10298755.19
#Sta/Elev= 30
  4371.1  1443.7  4409.1 1442.53  4661.2 1435.85  4704.6 1433.58    4754 1427.69
  4762.7 1428.15    4786 1424.12  4844.1 1418.84  4867.3 1418.41  4947.9 1409.23
  4990.8 1400.11  5009.3 1398.37  5009.8 1397.87  5027.5 1398.37  5027.8 1401.73
  5049.3 1403.72  5086.3 1401.96  5274.7  1409.3  5450.4  1411.6    5463 1413.23
  5672.3 1414.54    5933 1403.68  6314.2 1419.84  6591.9 1430.27  6682.3 1431.51
  6830.8  1430.1  6958.2 1436.98  7106.6 1440.69  7447.2 1461.52  7455.4 1462.65
#Mann= 9 ,-1 , 0
  4371.1     .12       0  4409.1     .05       0    4754     .12       0
  5009.3     .07       0  5027.5     .12       0  5274.7     .05       0
  6314.2     .12       0  6591.9     .05       0  7447.2     .12       0
Bank Sta=5009.3,5027.5
XS Rating Curve= 0 ,0
Exp/Cntr=0.3,0.1