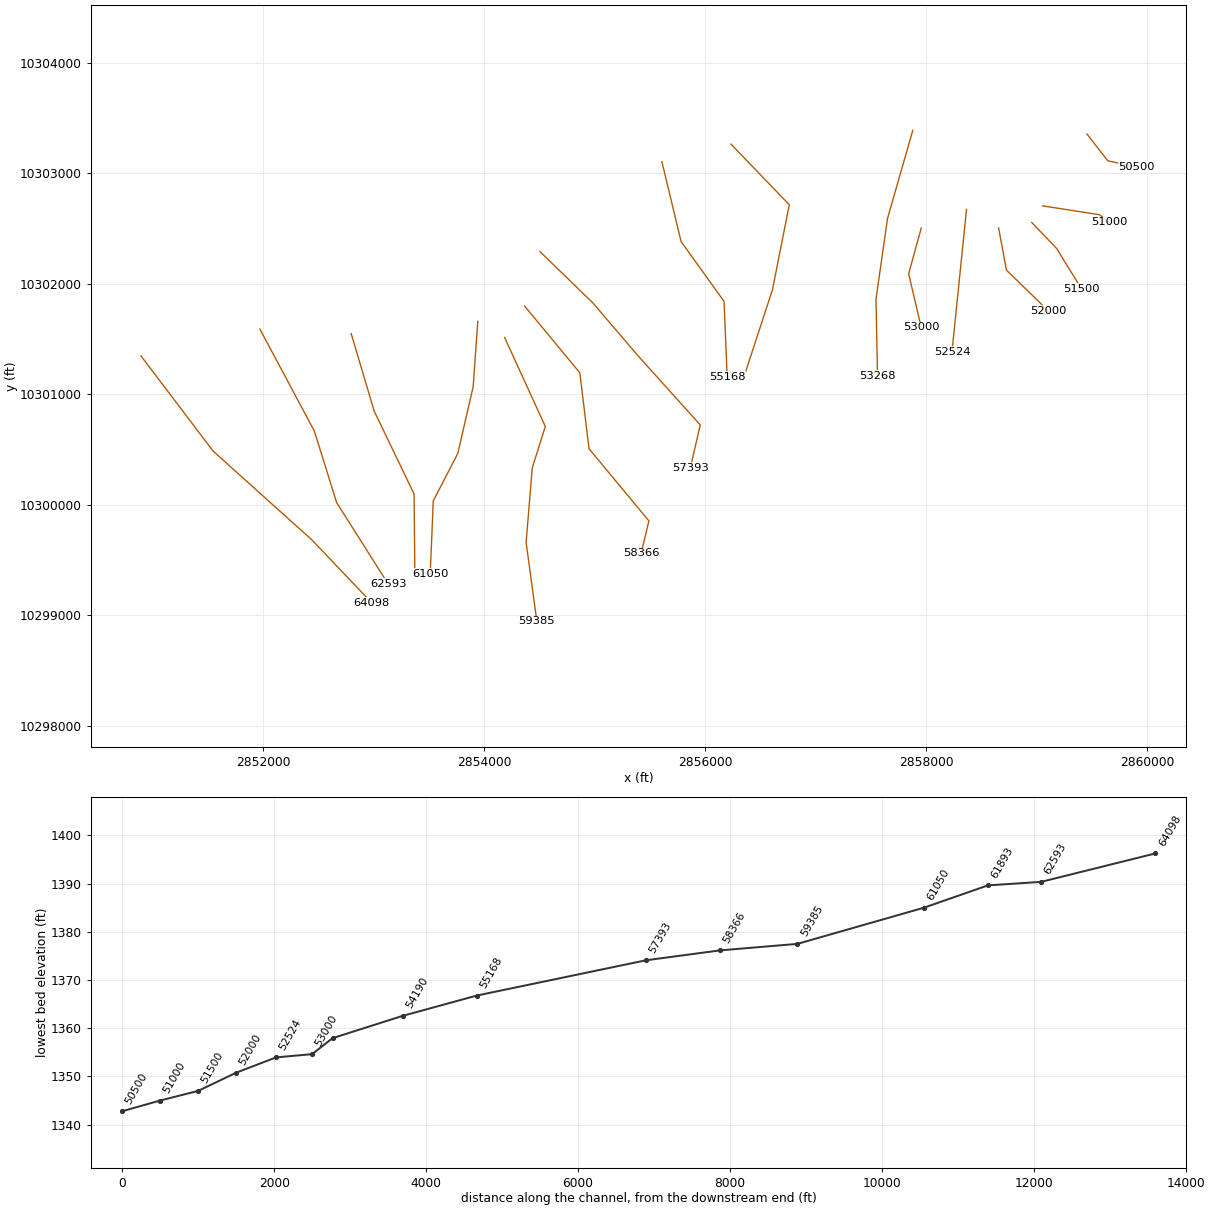
HEC-RAS study FALL CREEK.prj: FALL CREEK Base Level Engineering

--- FALL CREEK.g01 (geometry) --- (continued)

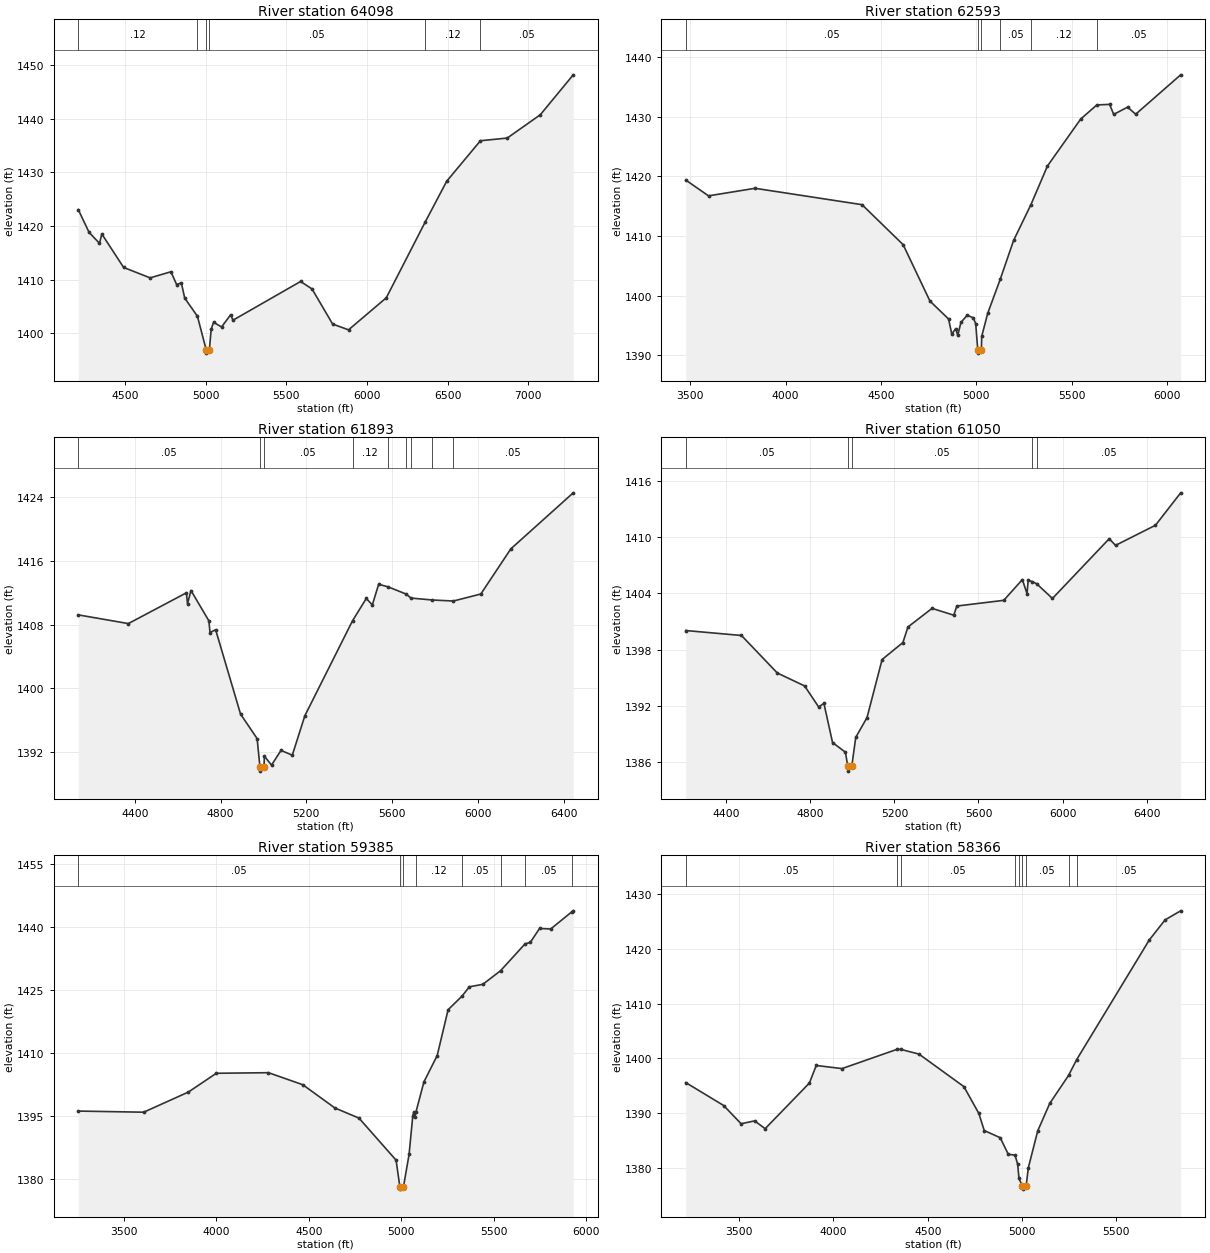
Type RM Length L Ch R = 1 ,64098   ,1505,1505,1505
BEGIN DESCRIPTION:
Mapping XS 6c47ec04
END DESCRIPTION:
XS GIS Cut Line= 4
      2850893.15     10301345.34      2851545.91     10300484.26
      2852441.75      10299678.7      2852982.02     10299110.72
#Sta/Elev= 30
  4209.3 1423.05  4276.3  1418.8  4340.8 1416.76  4355.3  1418.5  4490.5 1412.25
  4654.9 1410.31  4783.8 1411.45  4819.2 1409.05  4848.3 1409.39  4869.1 1406.54
  4948.1 1403.13  5003.5 1396.75    5004 1396.25  5021.7 1396.75  5033.5  1400.7
    5048 1402.01  5097.9 1401.14  5154.1 1403.42  5168.7  1402.4  5587.7 1409.63
  5658.7 1408.24  5786.5 1401.68  5885.1  1400.6  6119.1 1406.58  6359.4 1420.67
  6493.9 1428.36  6703.1 1435.92  6869.2 1436.42  7074.3 1440.77  7278.5 1448.23
#Mann= 6 ,-1 , 0
  4209.3     .12       0  4948.1     .05       0  5003.5     .05       0
  5021.7     .05       0  6359.4     .12       0  6703.1     .05       0
Bank Sta=5003.5,5021.7
XS Rating Curve= 0 ,0
Exp/Cntr=0.3,0.1

Type RM Length L Ch R = 1 ,62593   ,700,700,700
BEGIN DESCRIPTION:
Mapping XS ead573be
END DESCRIPTION:
XS GIS Cut Line= 4
      2851969.53     10301588.42      2852462.58     10300664.81
      2852663.97     10300018.98      2853129.24     10299282.87
#Sta/Elev= 30
  3476.6  1419.4    3596 1416.74  3839.9 1418.01  4400.8 1415.26  4616.2 1408.55
  4756.7 1399.09  4854.2 1396.08    4871 1393.58    4892 1394.44  4902.4 1393.32
  4919.2  1395.5  4951.7  1396.7  4984.3 1396.28  4996.7 1395.26  5007.4 1390.85
  5007.9 1390.35  5026.2 1390.85  5028.1 1393.17  5059.7 1397.05  5124.9 1402.72
  5195.3 1409.27  5285.8 1415.25  5372.6 1421.75  5546.9 1429.63  5631.6    1432
  5698.6 1432.09  5719.8 1430.41  5792.7 1431.63  5835.1 1430.44  6070.9 1437.05
#Mann= 6 ,-1 , 0
  3476.6     .05       0  5007.4     .05       0  5026.2     .05       0
  5124.9     .05       0  5285.8     .12       0  5631.6     .05       0
Bank Sta=5007.4,5026.2
XS Rating Curve= 0 ,0
Exp/Cntr=0.3,0.1

Type RM Length L Ch R = 1 ,61893   ,843,843,843
BEGIN DESCRIPTION:
Mapping XS 951a9c98
END DESCRIPTION:
XS GIS Cut Line= 4
       2852795.9      10301546.8      2853004.25     10300845.37
      2853365.36     10300095.37       2853372.3     10299352.32
#Sta/Elev= 30
    4137 1409.23  4370.3 1408.14  4640.9    1412  4646.1 1410.64  4662.4 1412.29
  4745.8 1408.48    4751 1407.01  4777.2 1407.37  4893.4 1396.78  4970.7  1393.7
  4983.9 1390.12  4984.4 1389.62  5002.7 1390.12  5004.4  1391.5  5037.7 1390.38
  5082.1 1392.22  5134.6 1391.62  5193.1 1396.57  5415.5  1408.5  5479.5 1411.29
  5507.7 1410.48  5537.1 1413.07  5581.1 1412.75  5665.6 1411.84  5687.9 1411.34
  5787.1  1411.1  5885.3 1410.97  6013.4 1411.85  6153.4 1417.52  6444.2 1424.55
#Mann= 9 ,-1 , 0
    4137     .05       0  4983.9     .03       0  5002.7     .05       0
  5415.5     .12       0  5581.1     .05       0  5665.6     .12       0
  5687.9     .05       0  5787.1     .12       0  5885.3     .05       0
Bank Sta=4983.9,5002.7
XS Rating Curve= 0 ,0
Exp/Cntr=0.3,0.1

Type RM Length L Ch R = 1 ,61050   ,1665,1665,1665
BEGIN DESCRIPTION:
Mapping XS 00158d95
END DESCRIPTION:
XS GIS Cut Line= 5
      2853941.75      10301657.9      2853900.08     10301067.59
      2853761.19     10300463.42      2853538.97     10300032.87
      2853511.19     10299373.17
#Sta/Elev= 30
  4206.1 1400.03  4471.5  1399.5    4642 1395.49  4772.3  1394.1  4839.1 1391.85
    4864 1392.24  4905.1 1388.05  4966.6 1387.01  4977.7 1385.49  4978.2 1384.99
  4996.6 1385.49  5015.6  1388.6  5069.3 1390.72  5141.1 1396.93    5240 1398.74
  5264.2 1400.41  5378.8  1402.4  5482.2 1401.67  5496.9 1402.65  5720.3 1403.26
  5808.9 1405.48    5831 1403.98  5836.7  1405.4  5856.5 1405.26  5876.7 1405.04
  5952.1 1403.46  6222.4 1409.85  6252.4 1409.14  6442.6 1411.29  6562.6 1414.76
#Mann= 5 ,-1 , 0
  4206.1     .05       0  4977.7     .05       0  4996.6     .05       0
  5856.5     .12       0  5876.7     .05       0
Bank Sta=4977.7,4996.6
XS Rating Curve= 0 ,0
Exp/Cntr=0.3,0.1

Type RM Length L Ch R = 1 ,59385   ,1019,1019,1019
BEGIN DESCRIPTION:
Mapping XS 62fee6f4
END DESCRIPTION:
XS GIS Cut Line= 5
      2854184.78     10301512.07      2854552.86     10300706.48
       2854434.8     10300331.48      2854379.25     10299657.87
      2854476.47     10298942.58
#Sta/Elev= 30
  3253.6  1396.1  3607.2 1395.83  3848.5 1400.62  4000.1 1405.11  4282.1 1405.25
  4467.8 1402.38  4641.2 1396.84  4771.6 1394.42  4972.3 1384.39  4992.8 1377.99
  4993.3 1377.49  5011.9 1377.99  5042.5 1385.77  5062.6    1395  5068.4 1395.89
  5073.4  1394.6  5079.7 1395.88  5122.8 1403.06  5194.5 1409.33  5253.5 1420.26
  5328.9 1423.51  5368.5 1425.73    5441 1426.31  5537.2 1429.56    5670 1435.98
  5697.6 1436.29    5748 1439.63  5808.3 1439.51  5923.8 1443.65  5930.2 1443.84
#Mann= 8 ,-1 , 0
  3253.6     .05       0  4992.8     .05       0  5011.9     .05       0
  5079.7     .12       0  5328.9     .05       0  5537.2     .12       0
    5670     .05       0  5923.8     .12       0
Bank Sta=4992.8,5011.9
XS Rating Curve= 0 ,0
Exp/Cntr=0.3,0.1

Type RM Length L Ch R = 1 ,58366   ,973,973,973
BEGIN DESCRIPTION:
Mapping XS bc5b1454
END DESCRIPTION:
XS GIS Cut Line= 5
      2854365.37     10301796.74      2854865.36     10301192.59
      2854948.69     10300505.09      2855490.36     10299852.31
      2855420.91     10299560.65
#Sta/Elev= 30
  3216.5  1395.6  3417.7 1391.41  3510.2 1388.08  3581.9  1388.6  3637.8 1387.18
  3872.3 1395.51  3908.8 1398.72  4045.2 1398.15  4334.8 1401.64  4355.7 1401.67
  4453.5  1400.8  4691.7 1394.86    4771 1389.96  4799.6 1386.84  4884.3 1385.53
  4927.2  1382.5  4962.8 1382.34  4976.7 1380.73  4983.9 1378.09  5002.3 1376.64
  5002.8 1376.14  5021.4 1376.64  5033.7 1380.08  5083.5  1386.8  5147.3 1391.81
  5246.7  1396.9  5289.1 1399.75  5674.5 1421.62  5758.8 1425.31  5841.3 1426.96
#Mann= 9 ,-1 , 0
  3216.5     .05       0  4334.8     .12       0  4355.7     .05       0
  4962.8     .12       0  4983.9     .05       0  5002.3     .05       0
  5021.4     .05       0  5246.7     .12       0  5289.1     .05       0
Bank Sta=5002.3,5021.4
XS Rating Curve= 0 ,0
Exp/Cntr=0.3,0.1

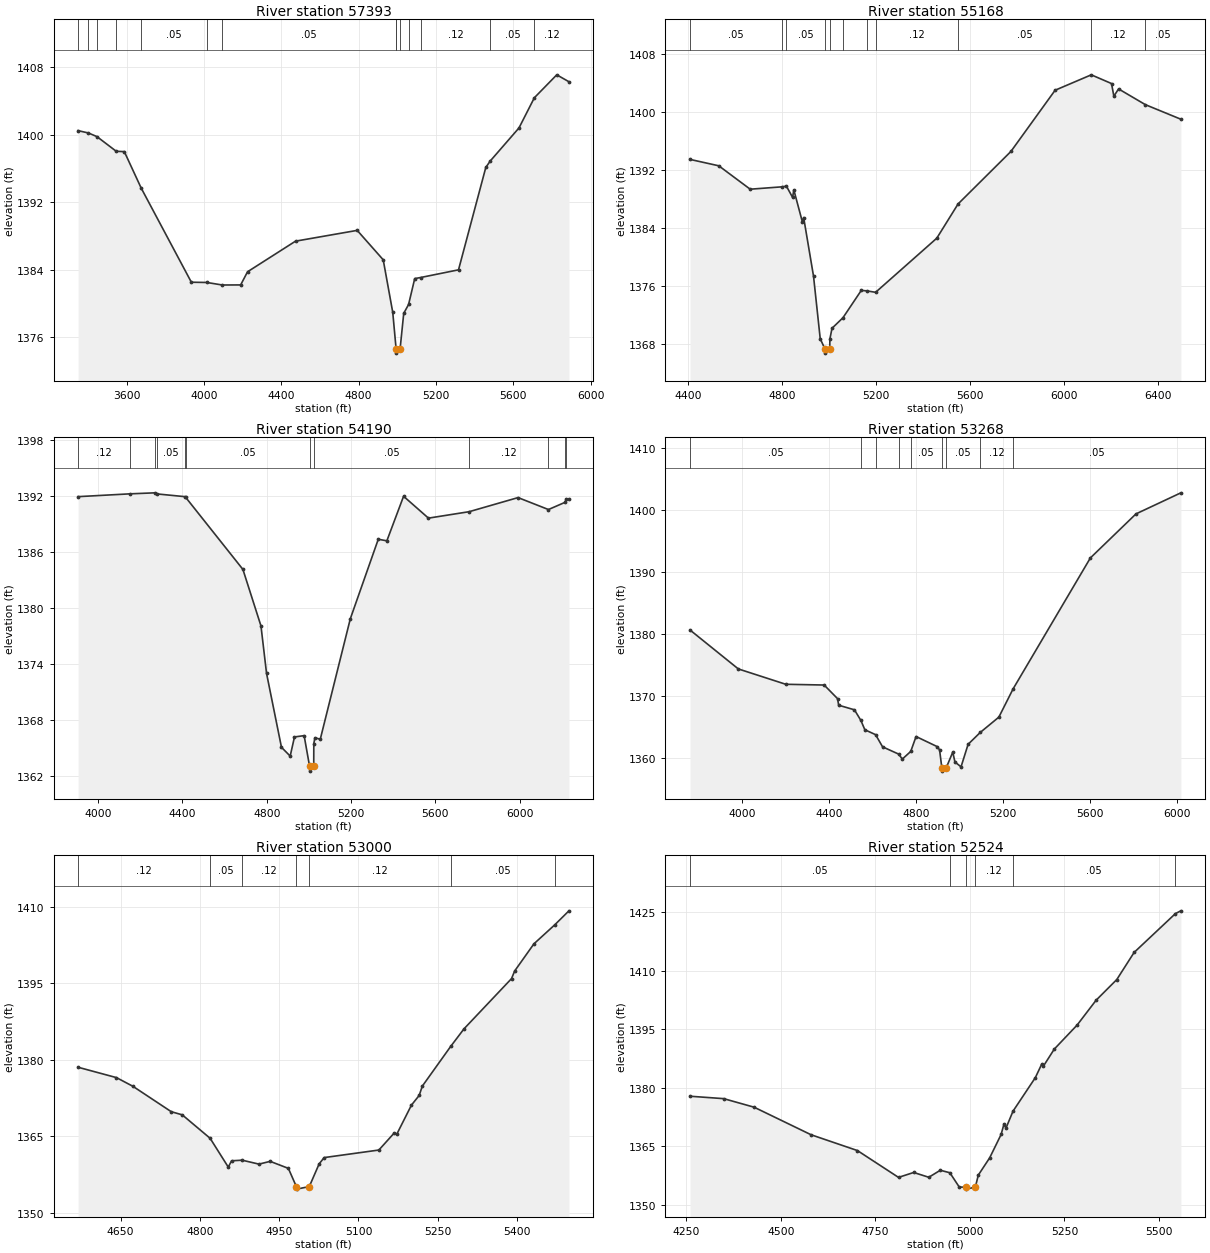
Type RM Length L Ch R = 1 ,57393   ,2225,2225,2225
BEGIN DESCRIPTION:
Mapping XS 9fb3b165
END DESCRIPTION:
XS GIS Cut Line= 5
      2854504.23     10302289.83      2854983.41     10301824.53
      2855393.14     10301345.37      2855955.64     10300720.37
      2855865.35     10300331.44
#Sta/Elev= 30
  3349.2 1400.48  3402.9  1400.2  3446.8 1399.77  3546.6 1398.03  3588.3 1397.99
  3675.9 1393.65    3935  1382.5  4015.1 1382.47  4095.1 1382.17    4190 1382.18
  4225.6 1383.74  4473.7 1387.37  4792.6 1388.65  4927.2 1385.16  4976.5 1378.93
  4993.3 1374.73  4995.3 1374.59  4995.8 1374.09  5014.5 1374.59  5033.3 1378.81
  5058.4 1379.86  5090.1 1382.93  5120.9 1383.06  5316.6 1383.97  5457.8 1396.12
  5481.1 1396.89  5629.3  1400.8  5708.8 1404.38  5824.7  1407.1  5887.7 1406.28
#Mann= 14 ,-1 , 0
  3349.2     .05       0  3402.9     .12       0  3446.8     .05       0
  3546.6     .12       0  3675.9     .05       0  4015.1     .12       0
  4095.1     .05       0  4993.3     .12       0  4995.3     .07       0
  5014.5     .12       0  5058.4     .05       0  5120.9     .12       0
  5481.1     .05       0  5708.8     .12       0
Bank Sta=4995.3,5014.5
XS Rating Curve= 0 ,0
Exp/Cntr=0.3,0.1

Type RM Length L Ch R = 1 ,55168   ,978,978,978
BEGIN DESCRIPTION:
Mapping XS 66826ec5
END DESCRIPTION:
XS GIS Cut Line= 4
      2855608.41     10303102.31      2855782.02     10302380.09
      2856170.91     10301838.42      2856198.69       10301158.
#Sta/Elev= 30
  4408.3 1393.44  4530.9 1392.56  4664.6 1389.34  4801.8 1389.67  4818.9 1389.76
  4845.2 1388.21  4850.4 1389.25  4887.2  1384.8  4892.3 1385.44  4934.3 1377.38
  4962.9 1368.76    4984 1367.28  4984.5 1366.78  5003.4 1367.28    5004 1368.72
  5013.1  1370.2  5059.7 1371.65  5137.7 1375.41  5161.1 1375.35  5198.8 1375.15
  5459.4  1382.6    5550 1387.31  5775.2 1394.54  5963.3 1402.96  6117.3 1405.08
  6203.5 1403.88  6213.5 1402.14  6233.6 1403.14    6348 1400.97  6498.9 1398.97
#Mann= 11 ,-1 , 0
  4408.3     .05       0  4801.8     .12       0  4818.9     .05       0
    4984     .05       0  5003.4     .05       0  5059.7     .12       0
  5161.1     .05       0  5198.8     .12       0    5550     .05       0
  6117.3     .12       0    6348     .05       0
Bank Sta=4984,5003.4
XS Rating Curve= 0 ,0
Exp/Cntr=0.3,0.1

Type RM Length L Ch R = 1 ,54190   ,922,922,922
BEGIN DESCRIPTION:
Mapping XS 1f3f0909
END DESCRIPTION:
XS GIS Cut Line= 4
      2856233.38     10303262.07      2856761.19     10302713.42
      2856608.41     10301942.59      2856365.37     10301199.57
#Sta/Elev= 30
  3904.9 1391.95  4149.6 1392.25  4269.8 1392.36  4280.5 1392.24  4411.4 1391.95
  4415.6 1391.87  4686.9 1384.16  4772.6 1378.11  4799.1 1373.02  4869.9 1365.11
  4911.2 1364.17  4931.6 1366.22  4977.4 1366.36  5003.4 1363.06  5003.9 1362.56
  5022.9 1363.06  5023.3 1365.51  5028.6 1366.14  5053.9 1365.97  5196.6 1378.88
  5329.2 1387.39  5369.9 1387.22  5449.2 1391.99  5567.2 1389.65  5760.3 1390.34
  5992.4 1391.85  6136.6 1390.57    6215 1391.34  6221.3 1391.69  6233.8 1391.65
#Mann= 12 ,-1 , 0
  3904.9     .12       0  4149.6     .05       0  4269.8     .12       0
  4280.5     .05       0  4411.4     .12       0  4415.6     .05       0
  5003.4     .05       0  5022.9     .05       0  5760.3     .12       0
  6136.6     .05       0    6215     .12       0  6221.3     .05       0
Bank Sta=5003.4,5022.9
XS Rating Curve= 0 ,0
Exp/Cntr=0.3,0.1

Type RM Length L Ch R = 1 ,53268   ,268,268,268
BEGIN DESCRIPTION:
Mapping XS 86392160
END DESCRIPTION:
XS GIS Cut Line= 4
      2857879.23     10303386.99      2857650.08     10302588.42
      2857545.91     10301859.26      2857559.77     10301166.46
#Sta/Elev= 30
  3758.4 1380.66  3980.9 1374.39  4199.4 1371.92  4376.2  1371.8  4437.7 1369.61
  4442.9 1368.55  4515.6 1367.81  4545.2  1366.1  4563.5  1364.6  4612.9 1363.81
  4645.1 1361.85  4719.2 1360.68    4736 1359.88  4774.8 1361.11  4799.3 1363.51
  4897.6 1361.87  4907.7 1361.34  4918.1 1358.44  4918.6 1357.94  4937.8 1358.44
  4968.3    1361  4978.4 1359.41  5006.4 1358.63    5039 1362.26    5095 1364.17
  5180.5 1366.63  5246.3 1371.19    5602 1392.26    5812 1399.35  6018.7 1402.74
#Mann= 9 ,-1 , 0
  3758.4     .05       0  4545.2     .12       0  4612.9     .05       0
  4719.2     .12       0  4774.8     .05       0  4918.1     .05       0
  4937.8     .05       0    5095     .12       0  5246.3     .05       0
Bank Sta=4918.1,4937.8
XS Rating Curve= 0 ,0
Exp/Cntr=0.3,0.1

Type RM Length L Ch R = 1 ,53000   ,476,476,476
BEGIN DESCRIPTION:
FALL CREEK 106.0
END DESCRIPTION:
XS GIS Cut Line= 3
      2857955.68      10302503.1      2857841.66     10302088.07
      2857955.69      10301603.1
#Sta/Elev= 30
  4569.6 1378.51  4642.2 1376.48  4673.3 1374.78  4745.9  1369.8  4766.6 1369.19
  4819.4 1364.59  4853.7 1358.95    4860 1360.18    4880  1360.3  4911.8 1359.53
    4933 1360.07  4967.4  1358.7  4982.5 1355.13    4983 1354.63    5007 1355.13
  5025.6 1359.57  5035.1 1360.81  5138.6 1362.29  5167.4  1365.6  5172.6 1365.41
  5200.3  1371.1  5214.9 1372.99  5220.8 1374.81  5274.4 1382.58  5299.7 1386.04
  5389.6 1395.88  5395.5 1397.37    5432  1402.7  5471.2  1406.4  5498.2 1409.16
#Mann= 7 ,-1 , 0
  4569.6     .12       0  4819.4     .05       0    4880     .12       0
  4982.5     .07       0    5007     .12       0  5274.4     .05       0
  5471.2     .12       0
Bank Sta=4982.5,5007
XS Rating Curve= 0 ,0
Exp/Cntr=0.3,0.1

Type RM Length L Ch R = 1 ,52524   ,524,524,524
BEGIN DESCRIPTION:
Mapping XS ffc95b73
END DESCRIPTION:
XS GIS Cut Line= 2
      2858365.36     10302671.74      2858233.41     10301380.06
#Sta/Elev= 30
  4259.5 1377.77  4348.6 1377.15    4429 1374.96  4579.8 1367.89  4702.3 1363.84
    4811 1356.96  4851.2 1358.22  4891.1 1356.99  4921.6 1358.79  4946.8 1358.15
  4971.8 1354.47  4989.7 1354.45  4990.2 1353.95  5014.2 1354.45  5022.1 1357.55
  5052.2 1361.98  5082.4 1367.96  5090.1 1370.68  5095.1 1369.56  5113.9 1373.94
  5172.9 1382.53  5189.5 1385.93  5194.5 1385.52  5223.1 1389.86  5283.4 1396.01
  5333.7 1402.39  5388.4 1407.69  5434.2 1414.64  5543.6 1424.61  5557.9 1425.31
#Mann= 6 ,-1 , 0
  4259.5     .05       0  4946.8     .12       0  4989.7     .07       0
  5014.2     .12       0  5113.9     .05       0  5543.6     .12       0
Bank Sta=4989.7,5014.2
XS Rating Curve= 0 ,0
Exp/Cntr=0.3,0.1

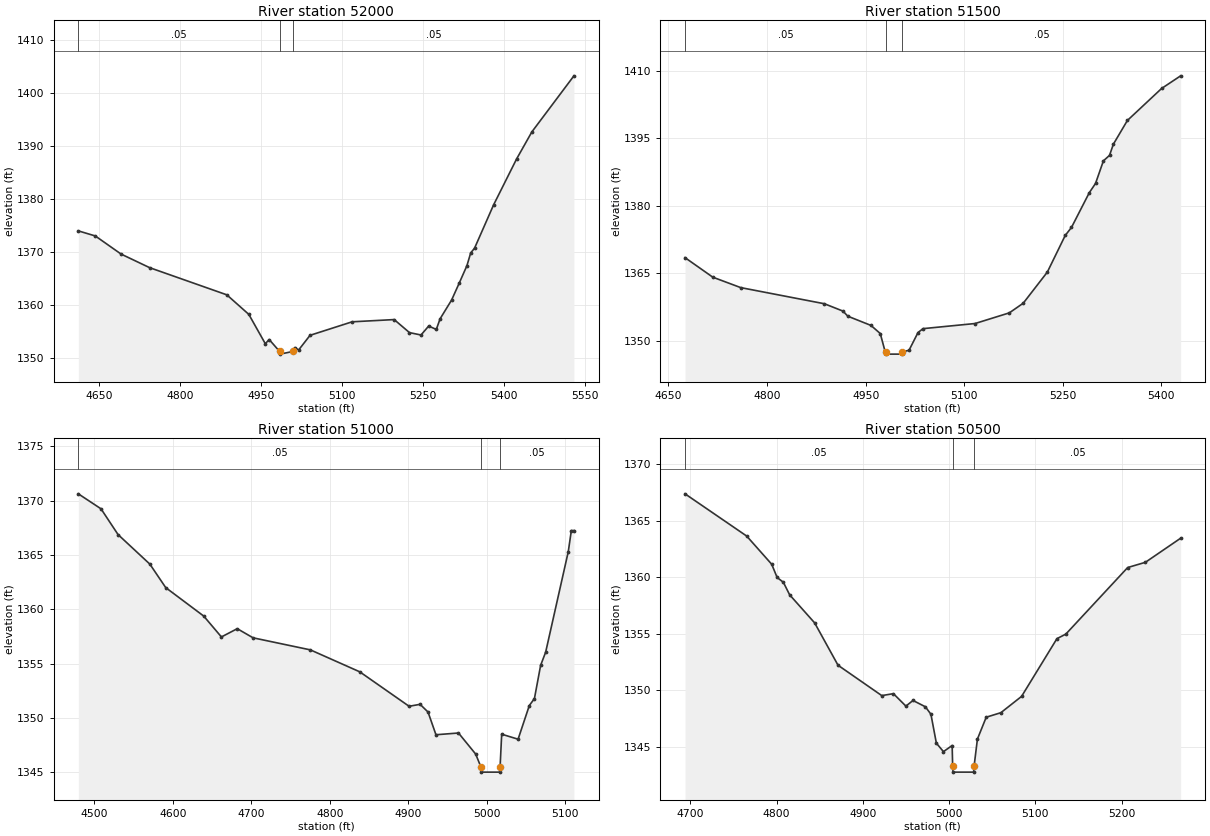
Type RM Length L Ch R = 1 ,52000   ,500,500,500
BEGIN DESCRIPTION:
FALL CREEK 104.0
END DESCRIPTION:
XS GIS Cut Line= 3
      2858655.69     10302503.08      2858726.68     10302121.93
      2859105.66     10301753.14
#Sta/Elev= 30
  4612.3 1374.04  4643.7 1373.08  4691.4 1369.66  4744.1  1367.1  4886.9 1361.97
  4927.6 1358.28  4958.1 1352.74  4965.2 1353.54  4984.6 1351.28  4985.1 1350.78
  5009.2 1351.28  5012.6 1352.02  5019.7 1351.56  5040.8 1354.33  5118.7 1356.88
  5196.4  1357.3  5224.7 1354.84    5246 1354.39  5260.2 1356.08  5274.3 1355.44
  5281.3 1357.45  5302.6 1360.99  5316.7 1364.19  5330.9 1367.47  5337.9 1369.88
    5345 1370.77  5380.3 1378.96  5422.7  1387.6    5451 1392.72  5528.8  1403.3
#Mann= 3 ,-1 , 0
  4612.3     .05       0  4984.6     .05       0  5009.2     .05       0
Bank Sta=4984.6,5009.2
XS Rating Curve= 0 ,0
Exp/Cntr=0.3,0.1

Type RM Length L Ch R = 1 ,51500   ,500,500,500
BEGIN DESCRIPTION:
FALL CREEK 103.0
END DESCRIPTION:
XS GIS Cut Line= 3
      2858955.68     10302553.12      2859180.21     10302318.42
      2859405.69      10301953.1
#Sta/Elev= 30
  4675.2 1368.48  4717.5 1364.13    4760 1361.81  4887.3 1358.22  4915.6 1356.58
  4922.9 1355.45  4958.1  1353.4  4972.3 1351.59  4979.5 1347.66    4981 1347.51
  4981.5 1347.01  5005.1 1347.01  5005.6 1347.51    5016 1347.86  5029.7 1351.81
  5037.3 1352.68  5116.5 1353.82  5168.6 1356.19  5189.8 1358.34  5226.5 1365.27
  5253.7 1373.42  5263.2  1375.2  5290.3 1382.93  5299.8 1384.99  5311.8 1390.02
  5321.1 1391.24    5327 1393.74  5348.3 1399.01  5400.3 1406.12  5429.3 1408.94
#Mann= 3 ,-1 , 0
  4675.2     .05       0    4981     .05       0  5005.6     .05       0
Bank Sta=4981,5005.6
XS Rating Curve= 0 ,0
Exp/Cntr=0.3,0.1

Type RM Length L Ch R = 1 ,51000   ,500,500,500
BEGIN DESCRIPTION:
FALL CREEK 102.0
END DESCRIPTION:
XS GIS Cut Line= 3
      2859055.68     10302703.11      2859569.69     10302623.07
      2859655.72     10302553.09
#Sta/Elev= 30
  4479.8 1370.62  4508.7 1369.24  4530.4 1366.87  4570.9 1364.15  4591.1 1361.99
  4639.5 1359.37    4662 1357.45  4682.2 1358.21  4702.3 1357.37  4775.3 1356.26
  4838.2 1354.24    4901 1351.07    4915 1351.25  4925.1 1350.54  4935.2 1348.45
  4963.9 1348.61  4985.8 1346.67  4992.3 1345.51  4992.8 1345.01  5016.4 1345.01
  5016.9 1345.51  5018.9  1348.5  5039.8 1348.04  5054.1 1351.14  5060.6 1351.78
  5068.5 1354.84  5074.9 1356.05  5103.7  1365.3  5107.6 1367.24  5110.9 1367.24
#Mann= 3 ,-1 , 0
  4479.8     .05       0  4992.3     .05       0  5016.9     .05       0
Bank Sta=4992.3,5016.9
XS Rating Curve= 0 ,0
Exp/Cntr=0.3,0.1

Type RM Length L Ch R = 1 ,50500   ,500,500,500
BEGIN DESCRIPTION:
FALL CREEK 101.0
END DESCRIPTION:
XS GIS Cut Line= 3
      2859455.66     10303353.14      2859643.57      10303111.5
      2859905.64     10303053.12
#Sta/Elev= 30
  4693.9 1367.37  4765.4 1363.64  4794.4 1361.15  4800.7 1359.98  4807.9 1359.56
  4815.2 1358.45  4844.2 1355.97  4871.3 1352.23    4922 1349.55  4935.5 1349.72
    4950 1348.62  4958.2 1349.12  4972.6 1348.56    4979  1347.9  4985.3 1345.35
  4993.5  1344.6  5003.6 1345.14  5004.2 1343.29  5004.7 1342.79  5028.5 1342.79
    5029 1343.29  5032.9 1345.71  5043.1 1347.64  5060.1 1348.04  5084.1 1349.48
  5125.1 1354.58  5135.4 1354.98  5207.1 1360.86  5227.6 1361.32  5268.5 1363.45
#Mann= 3 ,-1 , 0
  4693.9     .05       0  5004.2     .05       0    5029     .05       0
Bank Sta=5004.2,5029
XS Rating Curve= 0 ,0
Exp/Cntr=0.3,0.1