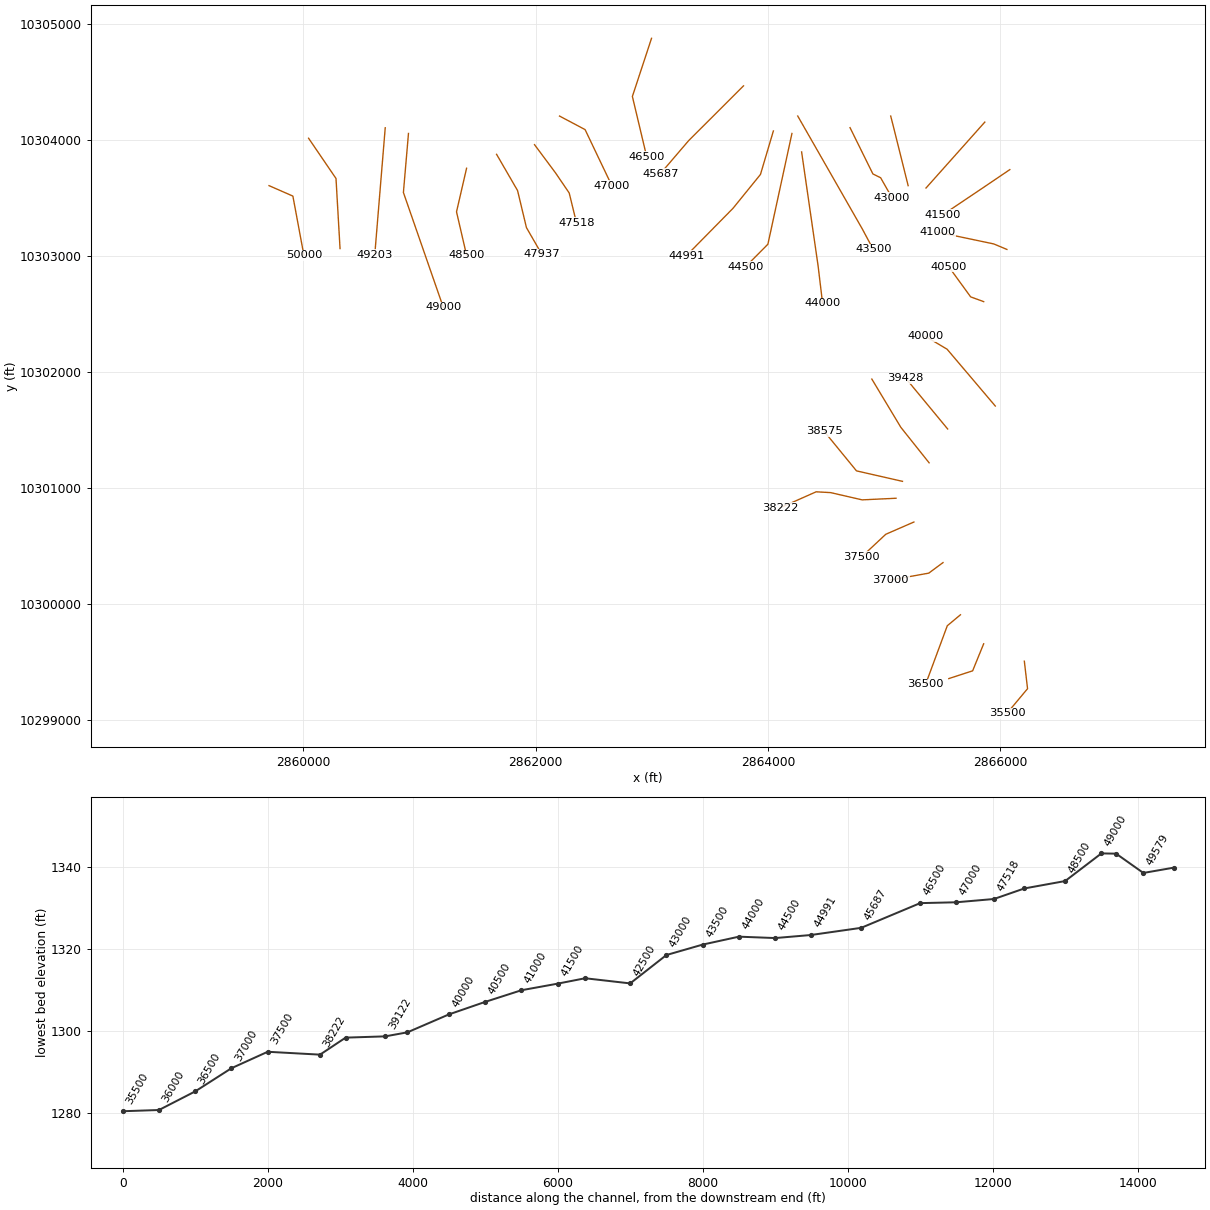
HEC-RAS study FALL CREEK.prj: FALL CREEK Base Level Engineering

--- FALL CREEK.g01 (geometry) --- (continued)

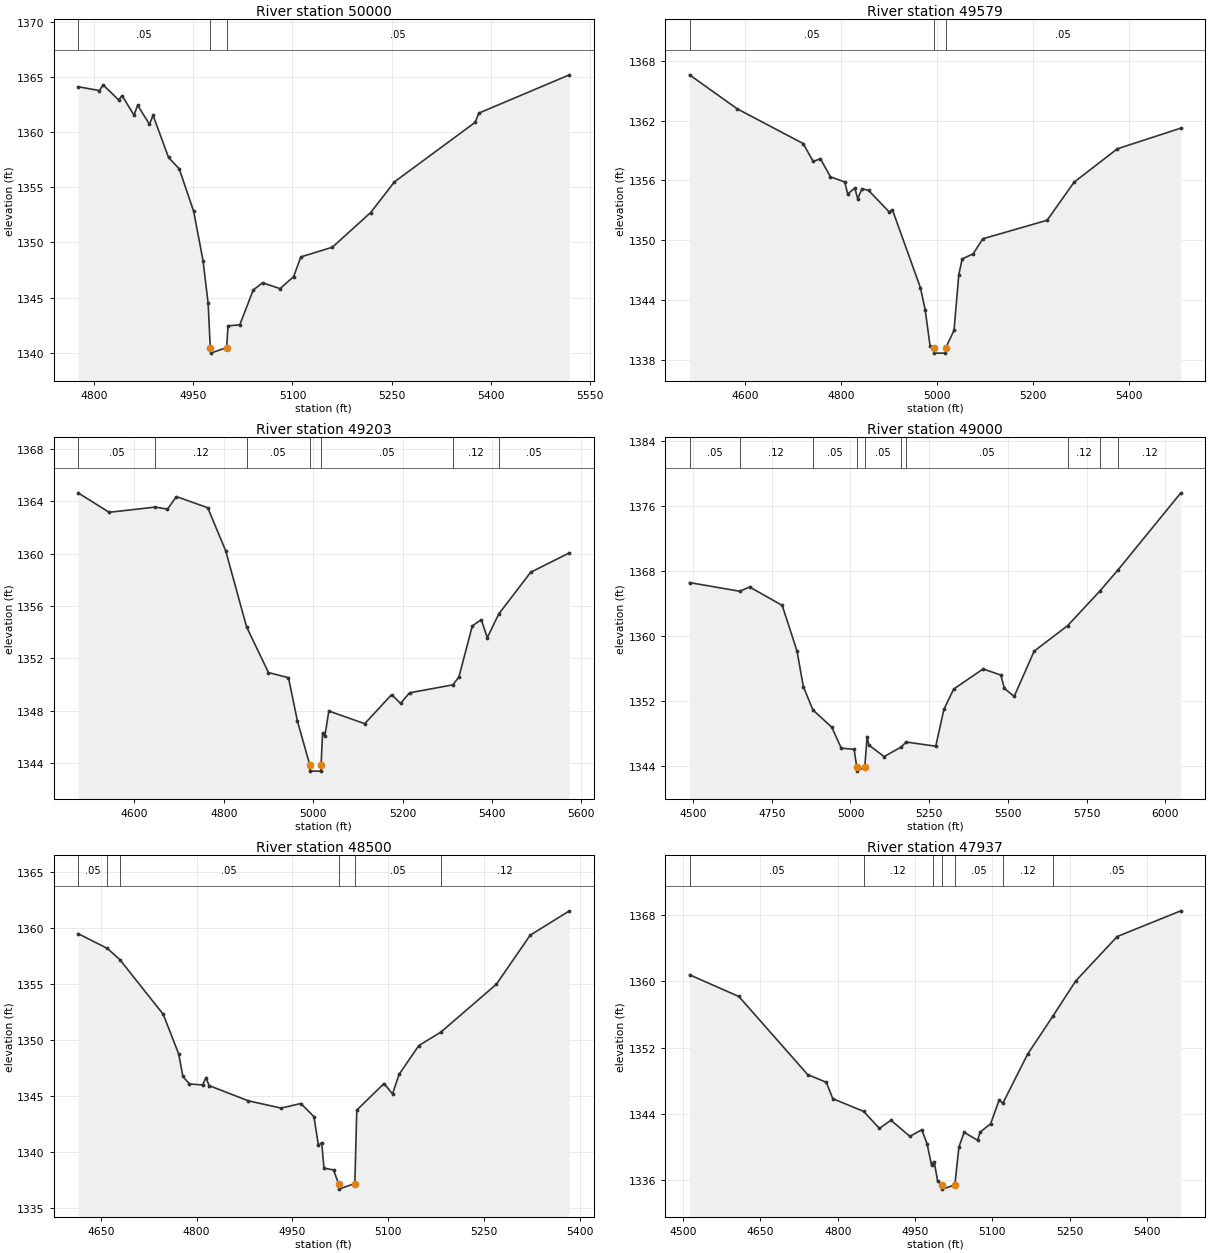
Type RM Length L Ch R = 1 ,50000   ,421,421,421
BEGIN DESCRIPTION:
FALL CREEK 100.0
END DESCRIPTION:
XS GIS Cut Line= 3
      2859705.69     10303603.11       2859910.9     10303513.06
      2860005.69     10303003.09
#Sta/Elev= 30
  4775.9 1364.15  4808.2  1363.8  4813.7 1364.32    4837 1362.96  4842.5 1363.33
  4860.4 1361.57  4865.9 1362.47  4883.8 1360.74  4889.2 1361.55  4912.6 1357.73
  4928.8 1356.69  4950.6 1352.83  4964.8 1348.34  4972.5 1344.46  4975.7 1340.45
  4976.2 1339.95  5000.5 1340.45  5002.5 1342.43  5020.3 1342.52  5040.6 1345.68
  5054.7 1346.34  5081.3 1345.81  5101.7  1346.9  5112.6 1348.69  5160.3 1349.57
  5218.2 1352.72  5254.2 1355.51  5376.3 1360.92  5381.6 1361.75  5518.7 1365.23
#Mann= 3 ,-1 , 0
  4775.9     .05       0  4975.7     .05       0  5000.5     .05       0
Bank Sta=4975.7,5000.5
XS Rating Curve= 0 ,0
Exp/Cntr=0.3,0.1

Type RM Length L Ch R = 1 ,49579   ,376,376,376
BEGIN DESCRIPTION:
Mapping XS 1a11afff
END DESCRIPTION:
XS GIS Cut Line= 3
      2860045.92     10304012.02      2860282.02     10303664.81
      2860316.74     10303060.68
#Sta/Elev= 30
  4484.2 1366.59  4583.6 1363.18  4721.3 1359.69  4742.3 1357.89  4757.2 1358.17
  4778.2 1356.35  4808.1 1355.83  4814.1 1354.63    4829 1355.22  4835.1 1354.15
    4844 1355.17  4857.8 1354.98  4900.9 1352.82  4907.4 1353.05  4965.9 1345.22
  4975.9 1342.99  4985.9 1339.41  4993.5 1339.15    4994 1338.65  5017.9 1338.65
  5018.4 1339.15    5036 1340.93    5046 1346.54    5053  1348.1  5076.1 1348.63
  5096.1 1350.13  5230.3 1351.99  5286.4 1355.81  5376.6 1359.16  5509.2 1361.24
#Mann= 3 ,-1 , 0
  4484.2     .05       0  4993.5     .03       0  5018.4     .05       0
Bank Sta=4993.5,5018.4
XS Rating Curve= 0 ,0
Exp/Cntr=0.3,0.1

Type RM Length L Ch R = 1 ,49203   ,203,203,203
BEGIN DESCRIPTION:
Mapping XS d9e21197
END DESCRIPTION:
XS GIS Cut Line= 2
      2860705.63     10304102.26      2860615.48     10303006.57
#Sta/Elev= 30
  4474.1 1364.66  4543.5 1363.17  4646.9 1363.57  4673.9 1363.41    4694 1364.37
  4764.2 1363.52  4804.4 1360.22  4850.9 1354.42    4900 1350.91  4944.8 1350.52
  4964.9 1347.19  4992.3 1343.87  4992.8 1343.37  5017.3 1343.37  5017.8 1343.87
  5021.2  1346.3  5026.2 1346.05  5035.1 1347.97  5115.4    1347  5175.6 1349.22
  5195.7 1348.55  5215.7 1349.36  5312.6 1349.97  5326.1 1350.57  5356.2 1354.48
  5376.3 1354.96  5389.7 1353.58  5415.3 1355.39  5486.7 1358.58  5573.5 1360.07
#Mann= 7 ,-1 , 0
  4474.1     .05       0  4646.9     .12       0  4850.9     .05       0
  4992.3     .05       0  5017.8     .05       0  5312.6     .12       0
  5415.3     .05       0
Bank Sta=4992.3,5017.8
XS Rating Curve= 0 ,0
Exp/Cntr=0.3,0.1

Type RM Length L Ch R = 1 ,49000   ,500,500,500
BEGIN DESCRIPTION:
FALL CREEK 98.0
END DESCRIPTION:
XS GIS Cut Line= 3
      2860905.68     10304053.09      2860862.03     10303544.06
      2861205.67     10302553.16
#Sta/Elev= 30
  4489.1 1366.61  4648.6 1365.54  4679.8 1366.07  4783.4  1363.8  4830.3 1358.19
  4850.4 1353.82  4880.9 1350.95  4940.7 1348.83  4970.8 1346.26  5011.6 1346.11
    5020 1343.93  5020.5 1343.43  5045.5 1343.93  5052.8 1347.68  5058.1 1346.65
  5106.8 1345.21  5161.8 1346.42  5176.9 1347.01  5270.7 1346.49  5296.6 1351.02
  5327.7 1353.52  5421.1 1355.99  5477.3 1355.24  5488.7  1353.6  5519.8 1352.62
  5583.1 1358.18  5689.1  1361.3  5791.5 1365.56  5850.3 1368.21  6048.8 1377.64
#Mann= 10 ,-1 , 0
  4489.1     .05       0  4648.6     .12       0  4880.9     .05       0
    5020     .05       0  5045.5     .05       0  5161.8     .12       0
  5176.9     .05       0  5689.1     .12       0  5791.5     .05       0
  5850.3     .12       0
Bank Sta=5020,5045.5
XS Rating Curve= 0 ,0
Exp/Cntr=0.3,0.1

Type RM Length L Ch R = 1 ,48500   ,563,563,563
BEGIN DESCRIPTION:
FALL CREEK 97.0
END DESCRIPTION:
XS GIS Cut Line= 3
      2861405.69     10303753.13      2861319.09     10303377.38
      2861405.69     10303003.07
#Sta/Elev= 30
  4614.4 1359.53  4660.4  1358.2  4679.7 1357.21  4747.8 1352.31  4771.9 1348.78
  4778.6 1346.75  4788.9 1346.08  4809.4 1345.99  4814.7 1346.64  4819.8 1345.93
  4881.2 1344.57  4932.5 1343.92  4963.3 1344.33  4983.9 1343.16  4990.9 1340.58
  4996.1 1340.83  4999.6 1338.54  5014.6 1338.39  5022.4 1337.17  5022.9 1336.67
    5048 1337.17    5051 1343.74  5093.7 1346.12    5107 1345.19  5117.3 1346.94
  5148.1 1349.51  5182.8 1350.72  5269.7    1355  5322.7 1359.39  5384.2 1361.57
#Mann= 6 ,-1 , 0
  4614.4     .05       0  4660.4     .12       0  4679.7     .05       0
  5022.4     .05       0    5048     .05       0  5182.8     .12       0
Bank Sta=5022.4,5048
XS Rating Curve= 0 ,0
Exp/Cntr=0.3,0.1

Type RM Length L Ch R = 1 ,47937   ,419,419,419
BEGIN DESCRIPTION:
Mapping XS b160ad5d
END DESCRIPTION:
XS GIS Cut Line= 4
      2861663.98     10303873.13      2861844.52     10303560.64
      2861920.91      10303241.2      2862052.87     10303012.02
#Sta/Elev= 30
  4512.3 1360.81  4608.1 1358.18  4741.6 1348.73  4777.9 1347.79  4790.4 1345.81
  4850.3 1344.27  4880.9 1342.21  4903.2  1343.2  4940.1 1341.25  4963.2 1342.05
  4973.5 1340.33  4982.1 1337.77  4984.8 1337.98  4987.3 1338.18    4994 1335.81
  5001.8 1335.36  5002.3 1334.86  5027.4 1335.36  5035.2 1339.93  5045.4 1341.74
  5071.4 1340.78  5076.6 1341.77  5096.9 1342.78  5113.5 1345.67  5120.5 1345.25
  5168.8 1351.22  5218.3 1355.86  5262.1 1360.07  5342.6 1365.44  5466.1 1368.55
#Mann= 7 ,-1 , 0
  4512.3     .05       0  4850.3     .12       0  4984.8     .05       0
  5001.8     .05       0  5027.4     .05       0  5120.5     .12       0
  5218.3     .05       0
Bank Sta=5001.8,5027.4
XS Rating Curve= 0 ,0
Exp/Cntr=0.3,0.1

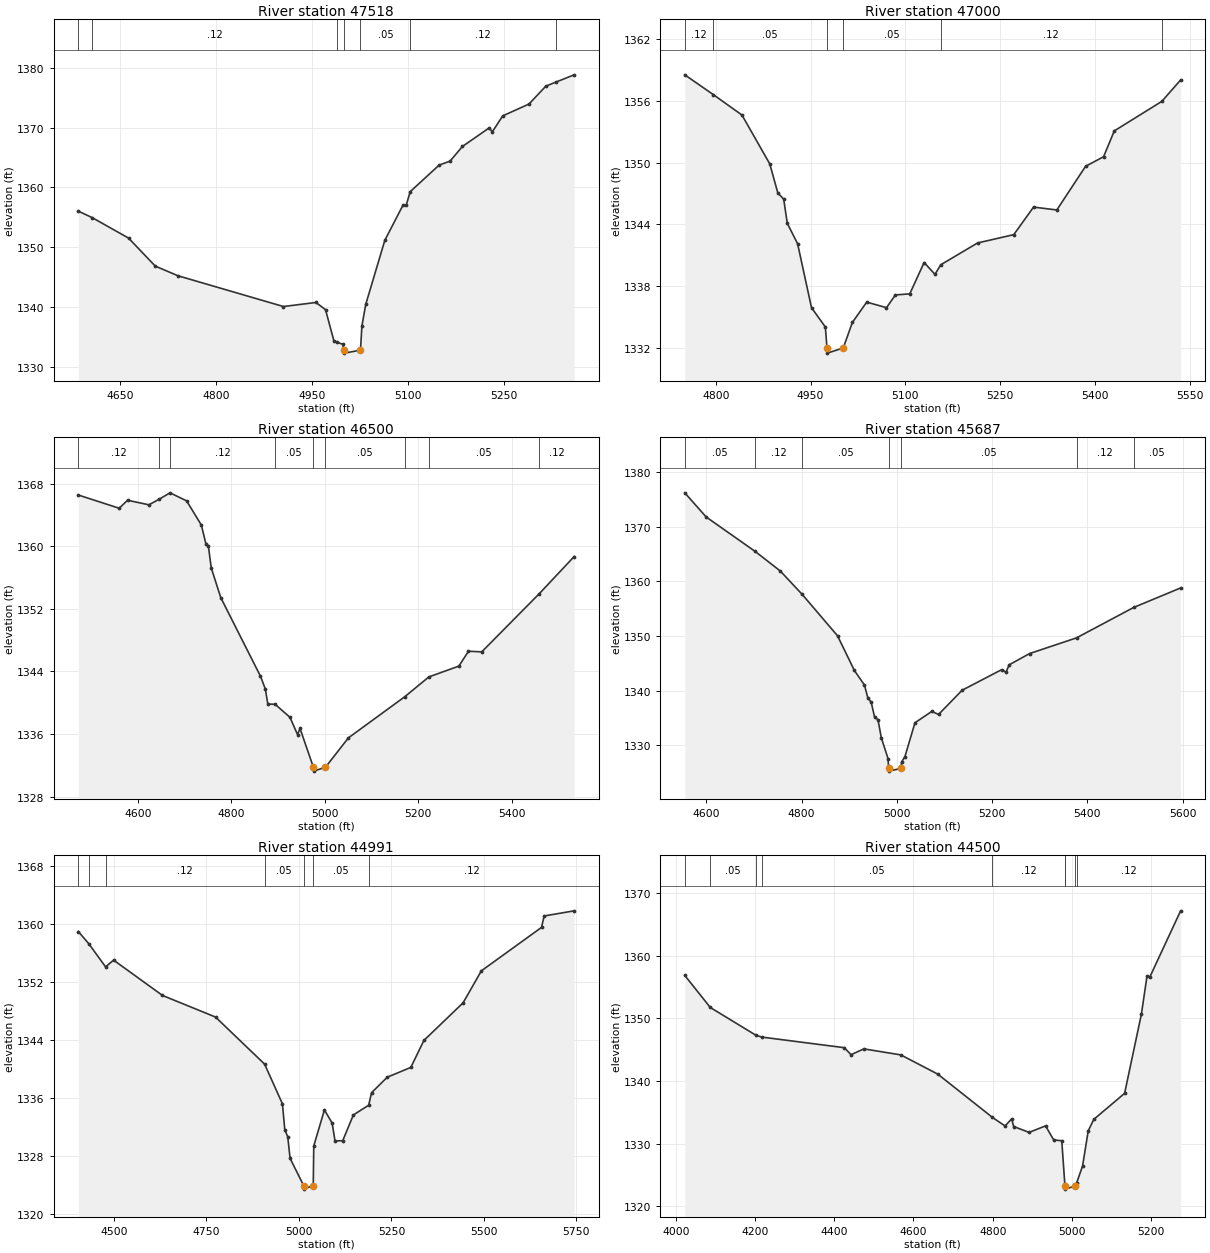
Type RM Length L Ch R = 1 ,47518   ,518,518,518
BEGIN DESCRIPTION:
Mapping XS bc6a2e44
END DESCRIPTION:
XS GIS Cut Line= 4
      2861990.33     10303956.51      2862170.91     10303713.42
      2862288.97     10303539.81      2862351.07     10303284.52
#Sta/Elev= 30
  4584.8 1356.02  4606.4 1354.94  4663.4 1351.51  4705.1 1346.83  4740.5 1345.22
  4905.6 1340.07  4956.4 1340.75  4971.4 1339.55  4984.7 1334.27  4989.4 1334.07
  4998.4 1333.78  5000.5 1332.78    5001 1332.28  5026.1 1332.78  5028.3 1336.79
  5034.3 1340.42  5064.2 1351.15  5092.5    1357  5097.6    1357  5103.9 1359.28
    5149 1363.71  5166.2 1364.38  5185.5 1366.83  5227.3 1369.93  5232.4 1369.29
  5248.5 1371.94  5289.7 1373.93  5315.9 1376.91  5331.2 1377.57  5360.3 1378.81
#Mann= 7 ,-1 , 0
  4584.8     .05       0  4606.4     .12       0  4989.4     .05       0
  5000.5     .05       0  5026.1     .05       0  5103.9     .12       0
  5331.2     .05       0
Bank Sta=5000.5,5026.1
XS Rating Curve= 0 ,0
Exp/Cntr=0.3,0.1

Type RM Length L Ch R = 1 ,47000   ,500,500,500
BEGIN DESCRIPTION:
FALL CREEK 94.0
END DESCRIPTION:
XS GIS Cut Line= 3
       2862205.7      10304203.1      2862425.55     10304086.41
      2862655.69     10303603.11
#Sta/Elev= 30
  4751.1 1358.54  4796.1 1356.62  4841.5 1354.63  4885.5 1349.88  4898.3 1347.04
  4907.5 1346.46  4913.2  1344.1  4929.5 1342.12  4951.5  1335.9  4973.4 1334.02
    4976 1331.98  4976.5 1331.48  5001.7 1331.98  5016.1 1334.46  5038.8 1336.44
  5070.1  1335.9  5084.2 1337.14  5106.9 1337.24  5129.6 1340.29  5146.8 1339.14
  5155.9 1340.07  5214.1 1342.19  5271.4    1343  5302.7 1345.68  5339.5  1345.4
  5384.9 1349.64  5413.5 1350.58  5430.4 1353.09  5505.6 1355.96  5535.3 1358.04
#Mann= 6 ,-1 , 0
  4751.1     .12       0  4796.1     .05       0    4976     .05       0
  5001.7     .05       0  5155.9     .12       0  5505.6     .05       0
Bank Sta=4976,5001.7
XS Rating Curve= 0 ,0
Exp/Cntr=0.3,0.1

Type RM Length L Ch R = 1 ,46500   ,813,813,813
BEGIN DESCRIPTION:
FALL CREEK 93.0
END DESCRIPTION:
XS GIS Cut Line= 3
      2862997.32     10304873.19       2862832.6     10304372.06
      2862955.67     10303853.16
#Sta/Elev= 30
  4472.5 1366.55  4559.9 1364.86  4577.8 1365.88  4623.5  1365.3  4644.7 1365.99
  4668.7 1366.83  4704.2  1365.8  4735.7 1362.71  4745.5  1360.3  4750.7 1360.05
  4756.8 1357.25  4777.3 1353.43  4862.1 1343.41  4872.6 1341.76  4877.9 1339.84
  4893.5 1339.81  4925.2 1338.15  4941.5 1335.94  4946.8 1336.72  4975.4 1331.77
  4975.9 1331.27  5001.3 1331.77  5050.3 1335.52  5171.2 1340.79  5222.5 1343.31
  5286.7 1344.69  5307.2 1346.59  5335.6 1346.51  5458.8 1353.95  5533.3 1358.69
#Mann= 9 ,-1 , 0
  4472.5     .12       0  4644.7     .05       0  4668.7     .12       0
  4893.5     .05       0  4975.4     .05       0  5001.3     .05       0
  5171.2     .12       0  5222.5     .05       0  5458.8     .12       0
Bank Sta=4975.4,5001.3
XS Rating Curve= 0 ,0
Exp/Cntr=0.3,0.1

Type RM Length L Ch R = 1 ,45687   ,696,696,696
BEGIN DESCRIPTION:
Mapping XS 0de4640c
END DESCRIPTION:
XS GIS Cut Line= 3
      2863788.94      10304463.4      2863316.75      10303991.2
      2863074.37     10303707.27
#Sta/Elev= 30
  4554.7 1376.25  4599.6 1371.82  4702.1 1365.53  4755.2 1361.92  4801.3 1357.62
  4875.4 1350.04  4910.8 1343.68    4932    1341    4939 1338.66  4946.1 1337.86
  4953.2 1335.13  4960.3 1334.67  4967.3 1331.36  4981.5 1327.51  4982.6 1325.73
  4983.1 1325.23  5008.6 1325.73  5009.8 1326.88  5016.8 1327.86    5038  1334.1
  5073.4 1336.18  5087.5 1335.62    5137 1340.06  5219.7 1343.82  5229.2 1343.37
  5235.8 1344.72  5278.6 1346.78  5377.2 1349.66  5497.3 1355.24  5595.8 1358.81
#Mann= 7 ,-1 , 0
  4554.7     .05       0  4702.1     .12       0  4801.3     .05       0
  4982.6     .05       0  5008.6     .05       0  5377.2     .12       0
  5497.3     .05       0
Bank Sta=4982.6,5008.6
XS Rating Curve= 0 ,0
Exp/Cntr=0.3,0.1

Type RM Length L Ch R = 1 ,44991   ,491,491,491
BEGIN DESCRIPTION:
Mapping XS e0717bf2
END DESCRIPTION:
XS GIS Cut Line= 4
       2864045.9      10304074.5       2863934.8     10303699.53
      2863698.69     10303407.87       2863295.9     10302998.13
#Sta/Elev= 30
  4403.4 1359.02  4431.2 1357.37  4477.2 1354.14  4498.7 1355.08    4631  1350.2
  4774.4 1347.22  4907.2 1340.72  4955.3 1335.25  4961.8 1331.65  4969.7  1330.7
  4976.1 1327.71  5012.7 1323.97  5013.2 1323.47  5038.7 1323.97  5040.1 1329.43
  5068.9  1334.4  5089.7  1332.6  5097.6 1330.13  5118.4 1330.15  5147.2 1333.71
  5188.6 1335.05  5196.4 1336.78  5238.9 1338.92  5302.6 1340.27  5337.9 1343.99
  5443.9 1349.18  5493.4  1353.6    5656 1359.59  5663.2 1361.17  5744.3 1361.88
#Mann= 7 ,-1 , 0
  4403.4     .12       0  4431.2     .05       0  4477.2     .12       0
  4907.2     .05       0  5012.7     .05       0  5038.7     .05       0
  5188.6     .12       0
Bank Sta=5012.7,5038.7
XS Rating Curve= 0 ,0
Exp/Cntr=0.3,0.1

Type RM Length L Ch R = 1 ,44500   ,500,500,500
BEGIN DESCRIPTION:
FALL CREEK 89.0
END DESCRIPTION:
XS GIS Cut Line= 3
      2864205.69     10304053.14      2863998.76      10303098.1
      2863805.69     10302903.11
#Sta/Elev= 30
  4022.8 1356.86  4087.2 1351.74  4202.8 1347.29  4217.6 1347.01  4425.6 1345.32
  4442.3  1344.2  4474.8 1345.13  4568.1 1344.17  4661.3  1341.1  4799.3 1334.19
  4831.2 1332.82  4847.9 1333.95    4853 1332.73  4891.9 1331.79  4933.5 1332.83
  4953.9  1330.6  4974.4 1330.45    4982 1323.59  4982.4 1323.23  4982.9 1322.73
  5008.5 1323.23  5011.7 1323.69  5026.9 1326.42  5041.1 1332.03  5055.2 1333.87
    5133 1338.03  5175.4 1350.68  5189.6 1356.77  5196.6  1356.6  5274.4 1367.18
#Mann= 9 ,-1 , 0
  4022.8     .12       0  4087.2     .05       0  4202.8     .12       0
  4217.6     .05       0  4799.3     .12       0    4982     .05       0
  4982.4     .05       0  5008.5     .05       0  5011.7     .12       0
Bank Sta=4982.4,5008.5
XS Rating Curve= 0 ,0
Exp/Cntr=0.3,0.1

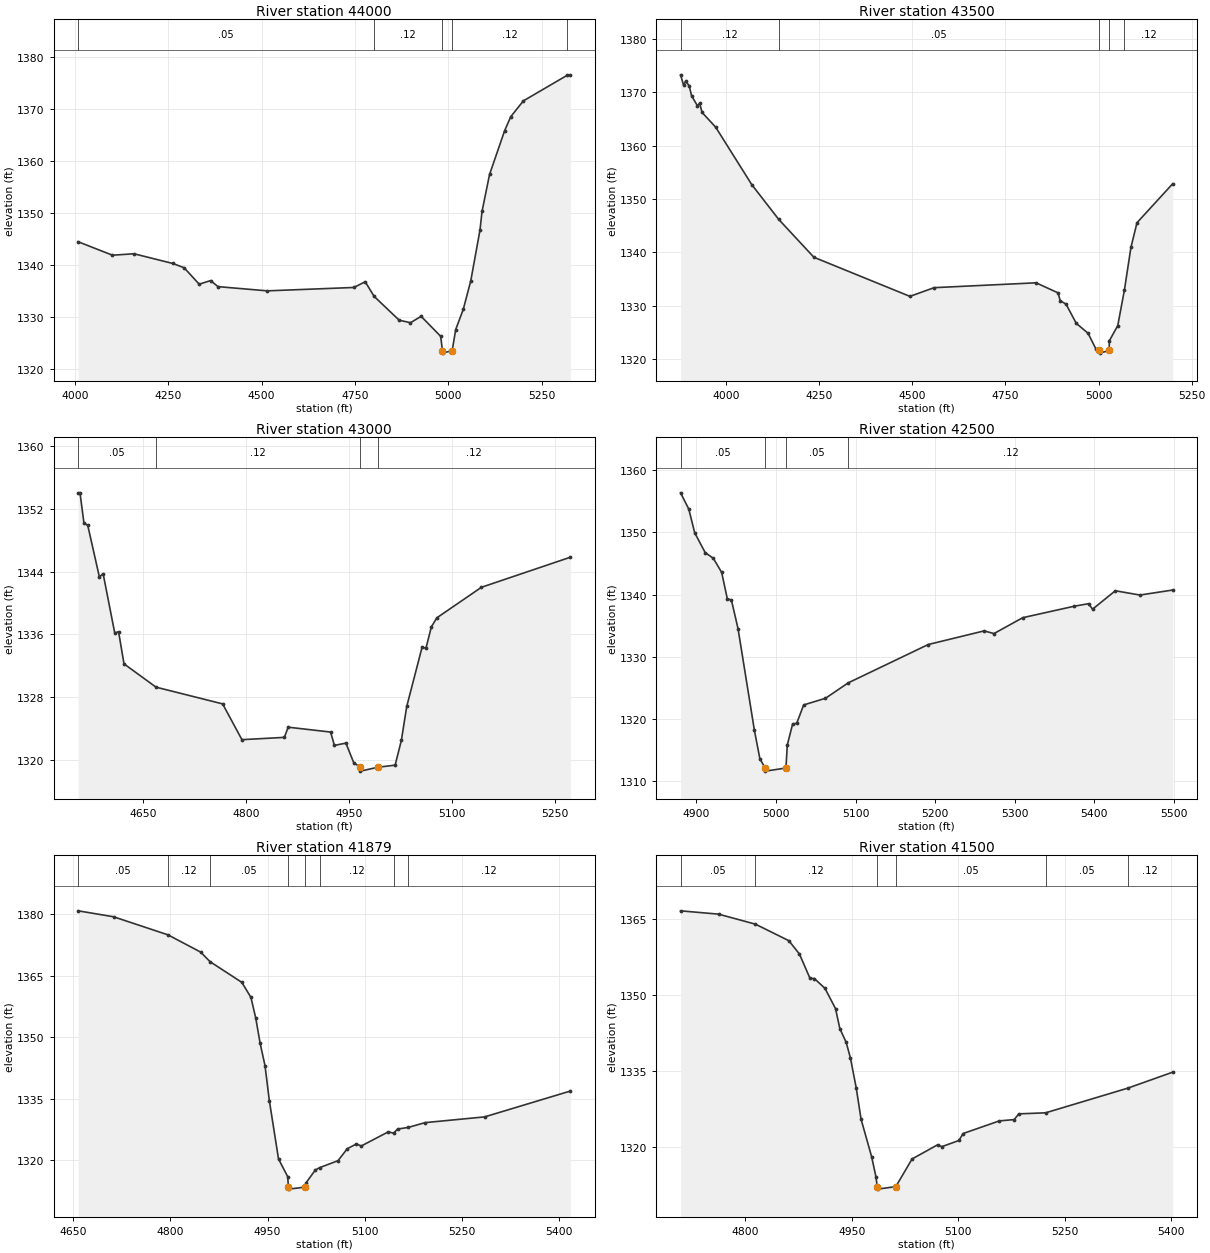
Type RM Length L Ch R = 1 ,44000   ,500,500,500
BEGIN DESCRIPTION:
FALL CREEK 88.0
END DESCRIPTION:
XS GIS Cut Line= 3
      2864288.96     10303894.01      2864430.63     10302912.68
      2864469.53     10302588.41
#Sta/Elev= 30
  4008.5 1344.46  4100.3 1341.88  4158.2 1342.15    4262 1340.29  4292.3 1339.47
  4332.7 1336.31    4363    1337  4383.2 1335.84    4515 1335.03    4747 1335.68
  4777.3 1336.78  4801.2 1333.97  4868.2  1329.4  4898.5 1328.91  4927.1 1330.14
  4979.4  1326.3  4984.2 1323.57  4984.7 1323.07  5010.3 1323.57  5019.7  1327.6
  5039.9 1331.47    5060 1336.94  5084.8 1346.74  5090.2 1350.29  5110.4  1357.4
  5150.6 1365.76  5167.1 1368.48    5201 1371.52  5318.4 1376.44  5326.6 1376.52
#Mann= 5 ,-1 , 0
  4008.5     .05       0  4801.2     .12       0  4984.2     .07       0
  5010.3     .12       0  5318.4     .05       0
Bank Sta=4984.2,5010.3
XS Rating Curve= 0 ,0
Exp/Cntr=0.3,0.1

Type RM Length L Ch R = 1 ,43500   ,500,500,500
BEGIN DESCRIPTION:
FALL CREEK 87.0
END DESCRIPTION:
XS GIS Cut Line= 3
      2864255.66     10304203.15      2864811.79     10303228.56
      2864905.69      10303053.1
#Sta/Elev= 30
  3877.9  1373.3  3885.9 1371.38  3891.6  1372.1    3901 1371.25  3907.5 1369.37
  3923.3 1367.48  3929.1 1367.98  3935.5 1366.26  3972.3 1363.47  4068.8 1352.74
  4141.2 1346.21  4235.8  1339.1  4493.6 1331.77  4558.4  1333.4  4832.1 1334.31
  4891.1 1332.43  4896.9 1330.98  4912.7  1330.3  4940.1 1326.71  4971.7 1324.86
  4993.4 1321.83  5002.3 1321.63  5002.8 1321.13  5028.4 1321.63  5028.9 1323.44
  5051.5  1326.3  5069.5 1333.03  5086.8 1340.94  5103.1 1345.58    5199 1352.89
#Mann= 5 ,-1 , 0
  3877.9     .12       0  4141.2     .05       0  5002.3     .05       0
  5028.4     .05       0  5069.5     .12       0
Bank Sta=5002.3,5028.4
XS Rating Curve= 0 ,0
Exp/Cntr=0.3,0.1

Type RM Length L Ch R = 1 ,43000   ,500,500,500
BEGIN DESCRIPTION:
FALL CREEK 86.0
END DESCRIPTION:
XS GIS Cut Line= 4
       2864705.7     10304103.07      2864902.31     10303704.08
      2864969.12     10303671.14      2865066.64     10303499.15
#Sta/Elev= 30
  4555.2 1354.05  4557.9 1354.05  4563.6 1350.23  4569.2  1349.9  4586.1 1343.34
  4591.6 1343.74  4608.5 1336.19  4614.1 1336.35    4622 1332.25  4668.7 1329.28
  4765.7 1327.15  4793.8 1322.59  4855.6 1322.88  4861.2 1324.18    4923 1323.56
  4928.5 1321.86  4945.3 1322.15  4956.6 1319.67    4966 1319.08  4966.5 1318.58
  4992.1 1319.08    5017 1319.34  5026.1  1322.5  5033.9 1326.82  5056.3 1334.38
  5061.9 1334.24  5069.8 1336.97  5077.8 1338.12  5142.7 1342.01  5272.2 1345.84
#Mann= 4 ,-1 , 0
  4555.2     .05       0  4668.7     .12       0    4966     .07       0
  4992.1     .12       0
Bank Sta=4966,4992.1
XS Rating Curve= 0 ,0
Exp/Cntr=0.3,0.1

Type RM Length L Ch R = 1 ,42500   ,621,621,621
BEGIN DESCRIPTION:
FALL CREEK 85.0
END DESCRIPTION:
XS GIS Cut Line= 3
      2865055.69     10304203.08      2865085.31     10304086.79
      2865205.68     10303603.15
#Sta/Elev= 30
    4880 1356.37  4890.3 1353.76  4897.8 1349.93  4910.9 1346.77  4921.2 1345.84
  4931.6 1343.59  4938.7 1339.36  4943.9 1339.13  4952.2 1334.54  4972.8 1318.18
  4979.6 1313.66  4986.2 1312.14  4986.7 1311.64  5012.4 1312.14  5014.1 1315.84
  5020.8 1319.22  5025.9 1319.32  5034.7 1322.28  5062.1 1323.35  5090.7 1325.83
  5191.2 1331.99  5261.4 1334.18  5273.8 1333.75  5309.9  1336.3  5374.8 1338.15
  5392.6 1338.55  5397.7 1337.67  5426.3 1340.63  5457.2 1339.94  5498.4 1340.75
#Mann= 4 ,-1 , 0
    4880     .05       0  4986.2     .05       0  5012.4     .05       0
  5090.7     .12       0
Bank Sta=4986.2,5012.4
XS Rating Curve= 0 ,0
Exp/Cntr=0.3,0.1

Type RM Length L Ch R = 1 ,41879   ,379,379,379
BEGIN DESCRIPTION:
Mapping XS 13d53e6a
END DESCRIPTION:
XS GIS Cut Line= 2
      2865865.33     10304150.89      2865359.52     10303582.72
#Sta/Elev= 30
  4657.3 1380.78    4712 1379.33    4796 1374.93  4846.6 1370.72  4861.3 1368.36
  4910.2 1363.35  4924.4 1359.66  4931.9 1354.54  4938.6 1348.46  4946.1 1343.04
  4952.8 1334.51    4967 1320.26  4981.2 1315.94  4982.3  1313.4  4982.8  1312.9
  5008.5  1313.4  5009.7 1314.47  5023.9 1317.56  5030.5 1318.14    5059 1319.84
  5073.2 1322.74  5087.4 1323.93  5094.9 1323.42  5136.8 1326.88  5144.8 1326.55
    5151 1327.55  5167.2 1327.94  5193.6 1329.12  5285.6 1330.52    5418 1336.82
#Mann= 8 ,-1 , 0
  4657.3     .05       0    4796     .12       0  4861.3     .05       0
  4982.3     .05       0  5008.5     .05       0  5030.5     .12       0
  5144.8     .05       0  5167.2     .12       0
Bank Sta=4982.3,5008.5
XS Rating Curve= 0 ,0
Exp/Cntr=0.3,0.1

Type RM Length L Ch R = 1 ,41500   ,500,500,500
BEGIN DESCRIPTION:
FALL CREEK 83.0
END DESCRIPTION:
XS GIS Cut Line= 3
      2866080.66     10303741.22      2865839.37     10303577.66
      2865505.69     10303353.11
#Sta/Elev= 30
  4708.5 1366.68  4762.1 1366.02    4814 1364.04  4861.1 1360.77    4876 1358.14
    4891 1353.29    4897 1353.28    4912 1351.34  4926.9 1347.32    4933 1343.37
  4941.9 1340.65  4947.9 1337.56  4956.1 1331.61  4962.9 1325.43  4977.8 1317.99
  4983.9 1314.02  4985.7 1312.08  4986.2 1311.58  5011.9 1312.08  5034.8 1317.55
  5070.8 1320.36  5076.8 1319.99  5100.8 1321.21  5106.8 1322.59  5157.8 1325.09
  5178.8 1325.35  5185.2 1326.48  5223.1 1326.69  5338.8 1331.57  5402.2 1334.74
#Mann= 6 ,-1 , 0
  4708.5     .05       0    4814     .12       0  4985.7     .07       0
  5011.9     .05       0  5223.1     .05       0  5338.8     .12       0
Bank Sta=4985.7,5011.9
XS Rating Curve= 0 ,0
Exp/Cntr=0.3,0.1

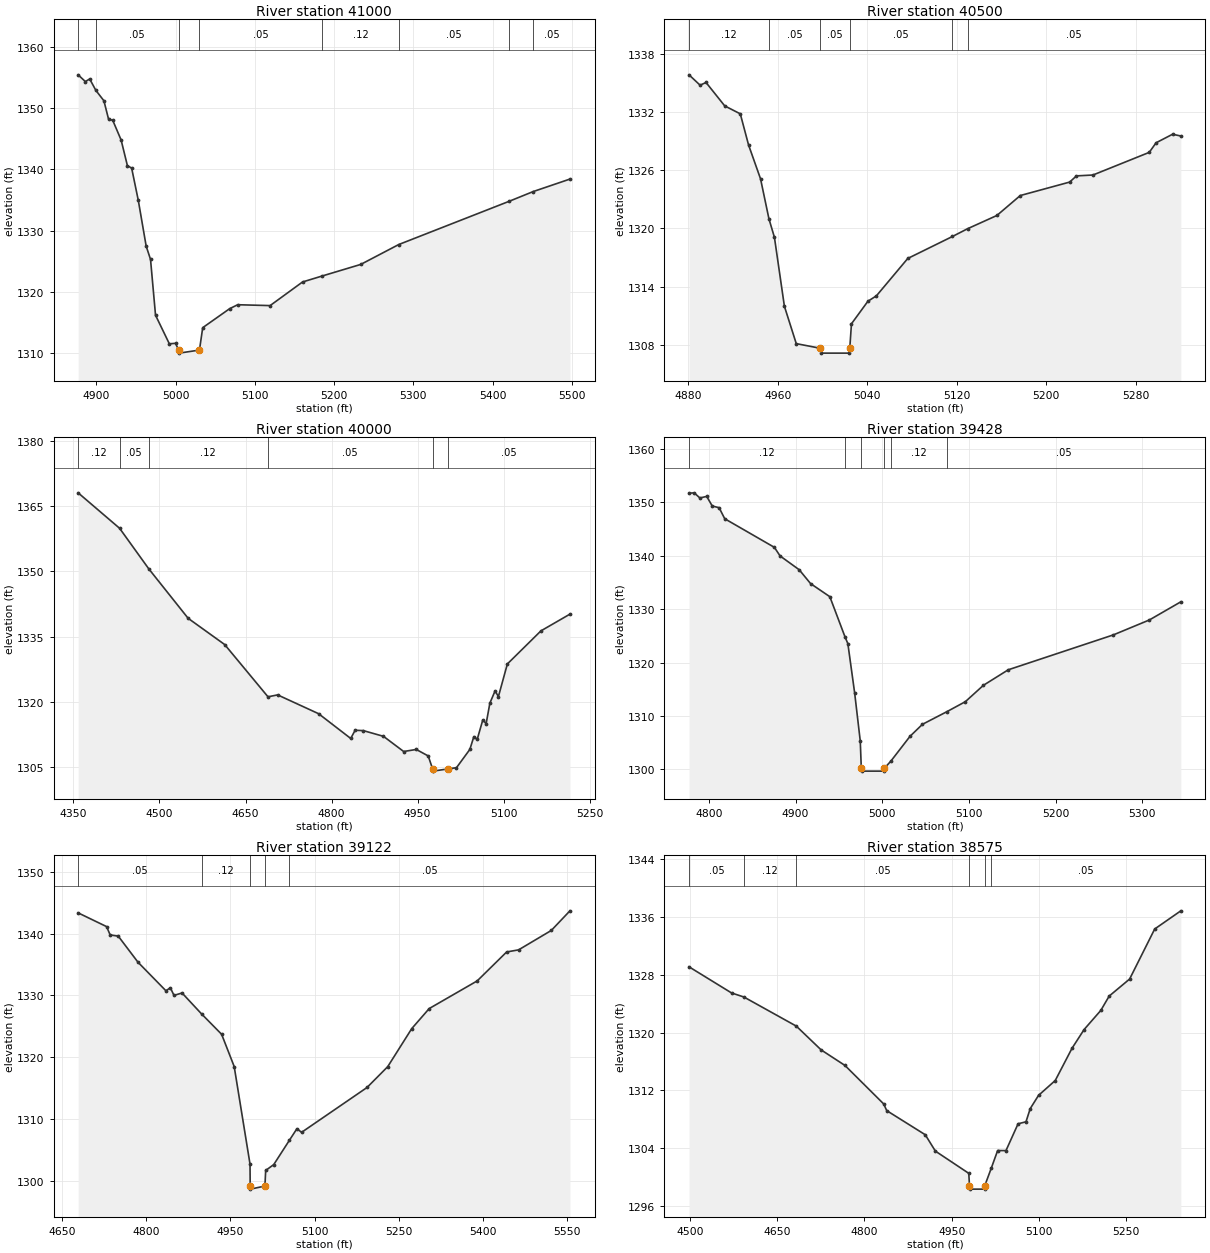
Type RM Length L Ch R = 1 ,41000   ,500,500,500
BEGIN DESCRIPTION:
FALL CREEK 82.0
END DESCRIPTION:
XS GIS Cut Line= 3
      2866055.65     10303053.13      2865942.43     10303100.67
      2865455.69     10303203.11
#Sta/Elev= 30
  4877.2 1355.46  4886.3 1354.36  4891.8 1354.78  4899.6 1352.91  4909.7 1351.22
  4915.5 1348.25  4920.9 1348.01  4931.4 1344.81  4939.3 1340.63  4944.7 1340.21
  4953.1 1334.92    4963 1327.46  4968.5 1325.29  4974.8 1316.17  4992.2  1311.5
    5000 1311.57    5004 1310.47  5004.5 1309.97  5030.2 1310.47  5034.3 1314.13
  5068.2 1317.23  5078.4 1317.88  5119.3 1317.74  5160.2  1321.6    5185 1322.58
  5233.6 1324.47  5281.5 1327.72  5420.6 1334.78  5451.1 1336.38  5497.4 1338.42
#Mann= 8 ,-1 , 0
  4877.2     .12       0  4899.6     .05       0    5004     .05       0
  5030.2     .05       0    5185     .12       0  5281.5     .05       0
  5420.6     .12       0  5451.1     .05       0
Bank Sta=5004,5030.2
XS Rating Curve= 0 ,0
Exp/Cntr=0.3,0.1

Type RM Length L Ch R = 1 ,40500   ,500,500,500
BEGIN DESCRIPTION:
FALL CREEK 81.0
END DESCRIPTION:
XS GIS Cut Line= 3
      2865855.67     10302603.12      2865743.74      10302644.1
      2865555.67     10302903.13
#Sta/Elev= 30
  4880.8 1335.87  4890.7  1334.8    4896 1335.08  4912.7 1332.66  4926.6 1331.84
    4934 1328.62  4944.7 1325.12  4952.2 1320.99  4957.1 1319.08    4966 1311.96
  4976.6  1308.1  4998.2 1307.62  4998.7 1307.12  5023.9 1307.12  5024.4 1307.62
  5025.9 1310.15  5040.6 1312.48  5048.2 1313.04  5076.2  1316.9  5116.1 1319.17
  5129.6 1319.97  5155.8 1321.34  5176.7  1323.4  5220.8 1324.79  5226.9 1325.43
  5241.6 1325.52  5291.9 1327.86    5298 1328.85  5312.7 1329.73  5320.1 1329.55
#Mann= 6 ,-1 , 0
  4880.8     .12       0  4952.2     .05       0  4998.2     .05       0
  5024.4     .05       0  5116.1     .12       0  5129.6     .05       0
Bank Sta=4998.2,5024.4
XS Rating Curve= 0 ,0
Exp/Cntr=0.3,0.1

Type RM Length L Ch R = 1 ,40000   ,572,572,572
BEGIN DESCRIPTION:
FALL CREEK 80.0
END DESCRIPTION:
XS GIS Cut Line= 3
      2865955.71     10301703.08        2865541.      10302192.9
      2865355.69     10302303.11
#Sta/Elev= 30
  4358.2 1368.02  4430.5 1359.87  4481.3 1350.56    4550 1339.18  4613.7 1333.15
  4689.2 1321.14    4706 1321.58  4777.4 1317.26  4833.4 1311.57  4841.1 1313.45
  4855.4 1313.37  4890.5 1312.06  4925.7 1308.57  4947.7 1309.04  4968.5 1307.55
  4976.2 1304.56  4976.7 1304.06  5002.5 1304.56  5017.8 1304.85  5041.1 1309.05
  5048.1    1312  5053.9 1311.34  5063.7 1315.84  5069.5 1314.96    5076 1319.68
  5085.1  1322.5  5090.9 1321.19  5106.5 1328.69    5165 1336.29  5215.6 1340.14
#Mann= 6 ,-1 , 0
  4358.2     .12       0  4430.5     .05       0  4481.3     .12       0
  4689.2     .05       0  4976.2     .05       0  5002.5     .05       0
Bank Sta=4976.2,5002.5
XS Rating Curve= 0 ,0
Exp/Cntr=0.3,0.1

Type RM Length L Ch R = 1 ,39428   ,306,306,306
BEGIN DESCRIPTION:
Mapping XS 20ac4304
END DESCRIPTION:
XS GIS Cut Line= 2
      2865545.88     10301505.13      2865184.82     10301942.57
#Sta/Elev= 30
  4777.1  1351.7  4783.1 1351.77  4789.6 1350.81  4797.5  1351.1  4803.9  1349.3
  4811.8 1348.99  4818.3 1346.92  4875.6 1341.56  4882.1 1339.96  4904.2 1337.37
  4917.3 1334.78  4939.5 1332.33    4957 1324.81  4960.3 1323.54  4968.1 1314.35
  4974.6 1305.32  4975.8 1300.18  4976.3 1299.68  5001.6 1299.68  5002.1 1300.18
  5009.7 1301.51    5032  1306.2  5046.3 1308.44  5074.3 1310.79  5095.8 1312.68
  5116.6 1315.74  5145.3 1318.65  5266.5 1325.18  5308.1 1327.98  5344.3 1331.37
#Mann= 6 ,-1 , 0
  4777.1     .12       0    4957     .05       0  4975.8     .05       0
  5002.1     .05       0  5009.7     .12       0  5074.3     .05       0
Bank Sta=4975.8,5002.1
XS Rating Curve= 0 ,0
Exp/Cntr=0.3,0.1

Type RM Length L Ch R = 1 ,39122   ,547,547,547
BEGIN DESCRIPTION:
Mapping XS cfaa6096
END DESCRIPTION:
XS GIS Cut Line= 3
       2865386.2     10301213.42      2865143.14     10301518.98
      2864893.11     10301935.68
#Sta/Elev= 30
  4678.5 1343.35  4729.2 1341.13  4735.6 1339.78    4750 1339.59  4785.2 1335.37
  4834.9 1330.76  4842.9 1331.24  4849.3 1330.01  4863.7  1330.4  4898.5 1327.01
  4934.2 1323.72  4956.6 1318.51  4984.8 1302.74  4985.1 1299.19  4985.6 1298.69
  5011.4 1299.19  5012.7 1301.71  5027.1 1302.66    5055 1306.59  5068.4 1308.46
  5076.7 1307.87  5193.3 1315.12  5230.2 1318.49    5273 1324.64  5304.1 1327.88
  5389.6 1332.35  5442.1 1337.03  5463.4 1337.37  5521.7 1340.51  5554.9 1343.68
#Mann= 5 ,-1 , 0
  4678.5     .05       0  4898.5     .12       0  4985.1     .07       0
  5011.4     .12       0    5055     .05       0
Bank Sta=4985.1,5011.4
XS Rating Curve= 0 ,0
Exp/Cntr=0.3,0.1

Type RM Length L Ch R = 1 ,38575   ,353,353,353
BEGIN DESCRIPTION:
Mapping XS 882dff96
END DESCRIPTION:
XS GIS Cut Line= 3
      2865156.99     10301053.71      2864761.19     10301143.98
      2864483.43     10301484.24
#Sta/Elev= 30
  4498.5 1329.08  4571.6 1325.47  4592.8 1324.91  4682.9 1320.89  4725.5 1317.61
  4766.5 1315.46  4833.1 1310.14  4838.3 1309.22  4904.5 1305.89  4921.9 1303.63
  4979.3 1300.56  4980.5 1298.88    4981 1298.38  5006.4 1298.38  5006.9 1298.88
  5017.9 1301.26  5028.9 1303.71  5043.2  1303.7    5064  1307.4  5077.6 1307.68
  5084.9  1309.5  5099.2 1311.33  5127.9 1313.38  5156.7 1317.83  5177.5 1320.42
  5206.2 1323.06  5220.6 1325.04  5255.7 1327.39  5298.8  1334.3  5343.7 1336.81
#Mann= 6 ,-1 , 0
  4498.5     .05       0  4592.8     .12       0  4682.9     .05       0
  4980.5     .07       0  5006.9     .05       0  5017.9     .05       0
Bank Sta=4980.5,5006.9
XS Rating Curve= 0 ,0
Exp/Cntr=0.3,0.1

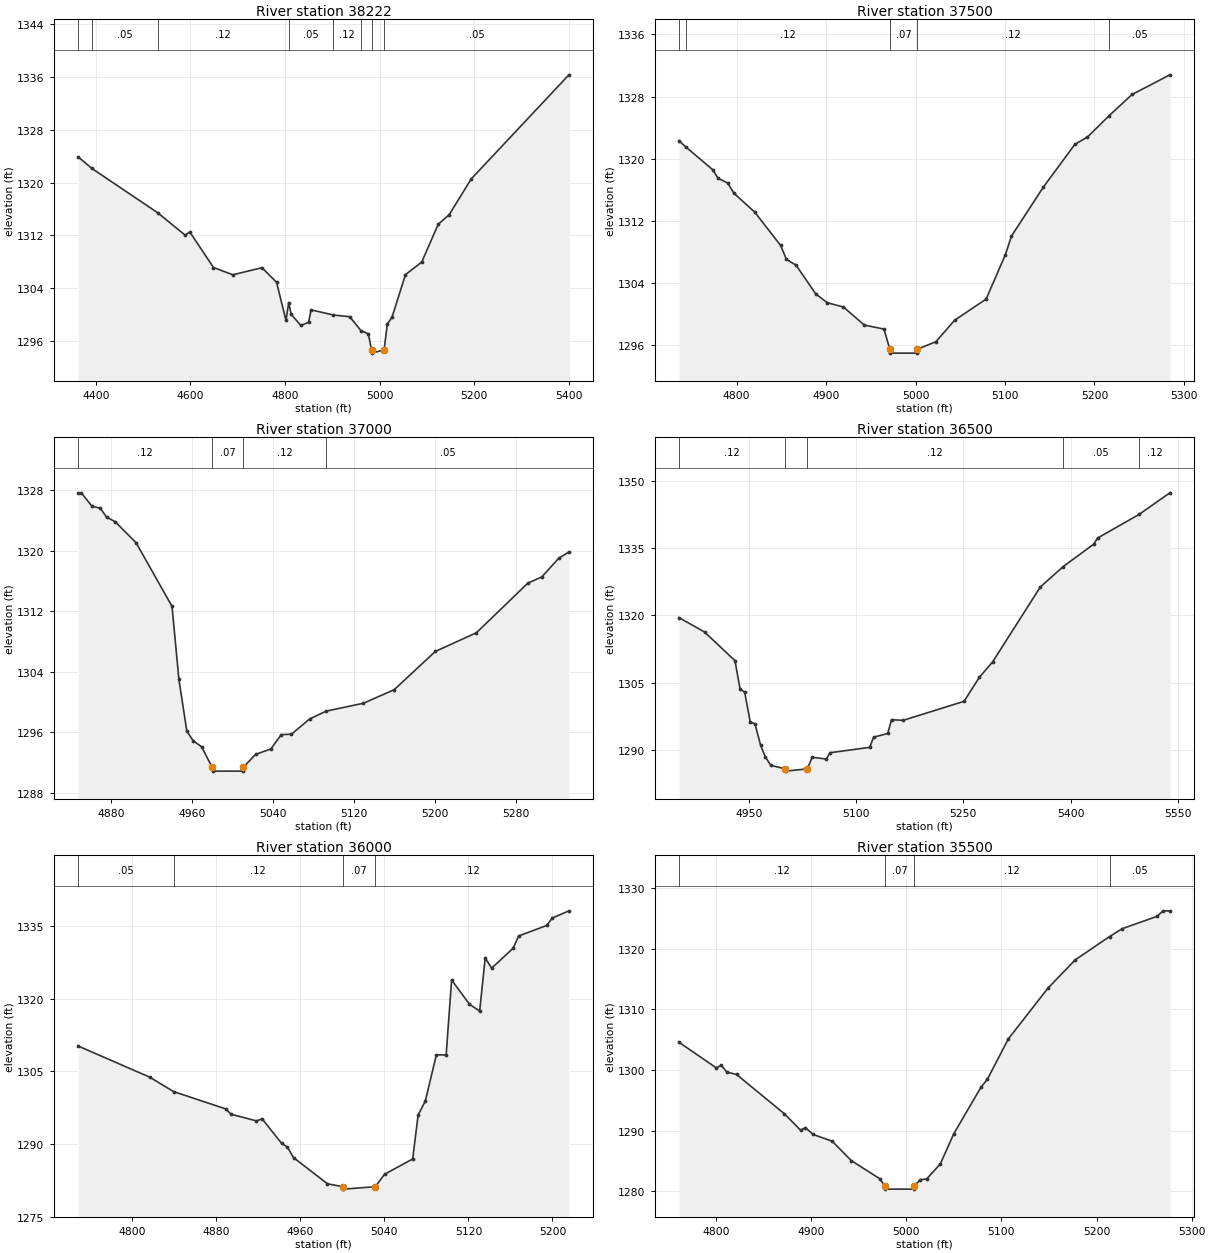
Type RM Length L Ch R = 1 ,38222   ,722,722,722
BEGIN DESCRIPTION:
Mapping XS 51caec93
END DESCRIPTION:
XS GIS Cut Line= 5
      2865101.48     10300907.87       2864809.8     10300893.98
      2864538.97     10300956.48      2864413.97     10300963.42
       2864101.5     10300824.55
#Sta/Elev= 30
  4362.7 1323.89  4391.9 1322.13  4530.6 1315.45  4588.8 1312.06  4598.8 1312.53
  4648.8 1307.16  4689.7 1306.06  4751.3 1307.13  4782.1 1304.92    4802 1299.16
  4807.7 1301.87  4812.9 1300.09  4833.4  1298.4  4849.9 1298.89    4855 1300.76
  4901.5 1299.99  4936.8 1299.72  4960.2 1297.63    4976 1297.13  4982.8 1294.72
  4983.3 1294.22  5009.3 1294.72  5016.1 1298.61  5026.1 1299.66  5054.5 1306.09
  5088.8 1307.98  5123.6 1313.69  5146.9 1315.15  5193.4 1320.55  5399.8 1336.28
#Mann= 8 ,-1 , 0
  4362.7     .12       0  4391.9     .05       0  4530.6     .12       0
  4807.7     .05       0  4901.5     .12       0  4960.2     .05       0
  4982.8     .05       0  5009.3     .05       0
Bank Sta=4982.8,5009.3
XS Rating Curve= 0 ,0
Exp/Cntr=0.3,0.1

Type RM Length L Ch R = 1 ,37500   ,500,500,500
BEGIN DESCRIPTION:
FALL CREEK 75.0
END DESCRIPTION:
XS GIS Cut Line= 3
      2865255.66      10300703.1      2865013.34     10300597.32
       2864805.7     10300403.13
#Sta/Elev= 30
  4735.6  1322.3  4743.4 1321.48  4773.4 1318.55  4779.2 1317.46  4790.1 1316.85
  4796.8 1315.55  4820.2  1313.1  4849.1 1308.81  4855.6 1307.02  4866.5 1306.25
  4888.3 1302.57  4901.4 1301.41  4919.3 1300.87  4942.7 1298.54  4964.7 1298.02
  4971.2 1295.42  4971.7 1294.92  5001.4 1294.92  5001.9 1295.42  5022.7 1296.39
  5043.7 1299.16  5078.9 1301.89  5100.4 1307.61  5107.2 1310.01  5142.9 1316.33
  5178.1 1321.84  5192.2 1322.78  5216.5 1325.55  5242.1 1328.27  5284.3  1330.8
#Mann= 5 ,-1 , 0
  4735.6     .05       0  4743.4     .12       0  4971.2     .07       0
  5001.9     .12       0  5216.5     .05       0
Bank Sta=4971.2,5001.9
XS Rating Curve= 0 ,0
Exp/Cntr=0.3,0.1

Type RM Length L Ch R = 1 ,37000   ,500,500,500
BEGIN DESCRIPTION:
FALL CREEK 74.0
END DESCRIPTION:
XS GIS Cut Line= 3
      2865505.72     10300353.14      2865383.17     10300262.21
      2865055.66     10300203.11
#Sta/Elev= 30
  4847.4 1327.61  4850.6 1327.61    4861 1325.86  4869.4 1325.57  4875.6  1324.4
    4884 1323.81  4904.8 1321.02  4940.3 1312.63  4947.1 1303.01  4954.9 1296.21
  4961.1 1294.91  4969.5 1294.12    4980  1291.4  4980.5  1290.9  5010.2  1290.9
  5010.7  1291.4    5023 1293.11  5038.1 1293.83  5048.3 1295.71  5058.4 1295.77
  5076.5 1297.79  5092.9 1298.82  5129.5 1299.85    5160 1301.64  5200.7 1306.69
  5241.3 1309.15  5292.1 1315.69    5306 1316.52  5322.6 1318.96  5332.8 1319.81
#Mann= 4 ,-1 , 0
  4847.4     .12       0    4980     .07       0  5010.7     .12       0
  5092.9     .05       0
Bank Sta=4980,5010.7
XS Rating Curve= 0 ,0
Exp/Cntr=0.3,0.1

Type RM Length L Ch R = 1 ,36500   ,500,500,500
BEGIN DESCRIPTION:
FALL CREEK 73.0
END DESCRIPTION:
XS GIS Cut Line= 3
       2865655.7     10299903.12      2865542.53     10299808.53
       2865355.7     10299303.16
#Sta/Elev= 30
  4852.5 1319.48  4888.3 1316.26  4930.7 1309.88  4937.8  1303.6  4944.3 1302.81
  4952.1 1296.17  4958.6  1295.8  4966.4  1291.1  4972.9 1288.49  4980.7 1286.54
    5001 1285.73  5001.5 1285.23  5031.9 1285.73  5038.6 1288.33  5058.4 1287.92
  5063.7 1289.34  5119.2 1290.54  5124.5  1292.8  5144.3 1293.64  5149.6 1296.72
  5165.7 1296.56    5251 1300.81  5272.3 1306.14    5291 1309.62  5357.6 1326.32
  5389.3 1330.84  5432.2 1335.87  5437.7 1337.24  5495.7 1342.52  5538.8 1347.34
#Mann= 5 ,-1 , 0
  4852.5     .12       0    5001     .07       0  5031.9     .12       0
  5389.3     .05       0  5495.7     .12       0
Bank Sta=5001,5031.9
XS Rating Curve= 0 ,0
Exp/Cntr=0.3,0.1

Type RM Length L Ch R = 1 ,36000   ,500,500,500
BEGIN DESCRIPTION:
FALL CREEK 72.0
END DESCRIPTION:
XS GIS Cut Line= 3
      2865855.68     10299653.11      2865760.76       10299420.
      2865555.69     10299353.11
#Sta/Elev= 30
  4748.3 1310.26  4816.5 1303.82  4839.2 1300.84  4888.7 1297.27  4894.1 1296.15
  4918.2 1294.78  4923.6  1295.2  4942.2 1290.12  4947.6 1289.37  4953.5 1287.19
  4985.8 1281.78  5000.4 1281.18  5000.9 1280.68  5031.3 1281.18  5040.2 1283.76
  5066.9 1286.91  5072.1 1295.96    5079 1298.92  5089.5 1308.44  5098.8  1308.4
    5104  1323.9    5121 1318.89  5130.7 1317.47    5136 1328.44  5142.1 1326.34
  5162.6 1330.46  5167.9    1333  5194.5 1335.16  5199.8 1336.68  5215.7 1338.19
#Mann= 4 ,-1 , 0
  4748.3     .05       0  4839.2     .12       0  5000.4     .07       0
  5031.3     .12       0
Bank Sta=5000.4,5031.3
XS Rating Curve= 0 ,0
Exp/Cntr=0.3,0.1

Type RM Length L Ch R = 1 ,35500   ,500,500,500
BEGIN DESCRIPTION:
FALL CREEK 71.0
END DESCRIPTION:
XS GIS Cut Line= 3
      2866205.69     10299503.07      2866233.29     10299265.87
      2866055.71     10299053.14
#Sta/Elev= 30
  4761.2 1304.57  4800.4 1300.35  4805.4 1300.79  4811.5 1299.66  4821.6 1299.27
  4871.9  1292.8    4889 1290.08    4894 1290.52  4902.1 1289.39  4922.2 1288.27
  4942.4 1285.06  4972.5 1282.06  4977.3 1280.88  4977.8 1280.38  5007.7 1280.38
  5008.2 1280.88  5014.9 1281.94  5021.4 1282.05  5035.7 1284.51    5050 1289.51
  5078.7 1297.21  5085.2 1298.46  5107.3 1305.13  5148.9 1313.48  5177.6 1318.15
  5213.8    1322    5227 1323.29  5263.5 1325.31    5270 1326.23  5277.1 1326.21
#Mann= 4 ,-1 , 0
  4761.2     .12       0  4977.3     .07       0  5008.2     .12       0
  5213.8     .05       0
Bank Sta=4977.3,5008.2
XS Rating Curve= 0 ,0
Exp/Cntr=0.3,0.1