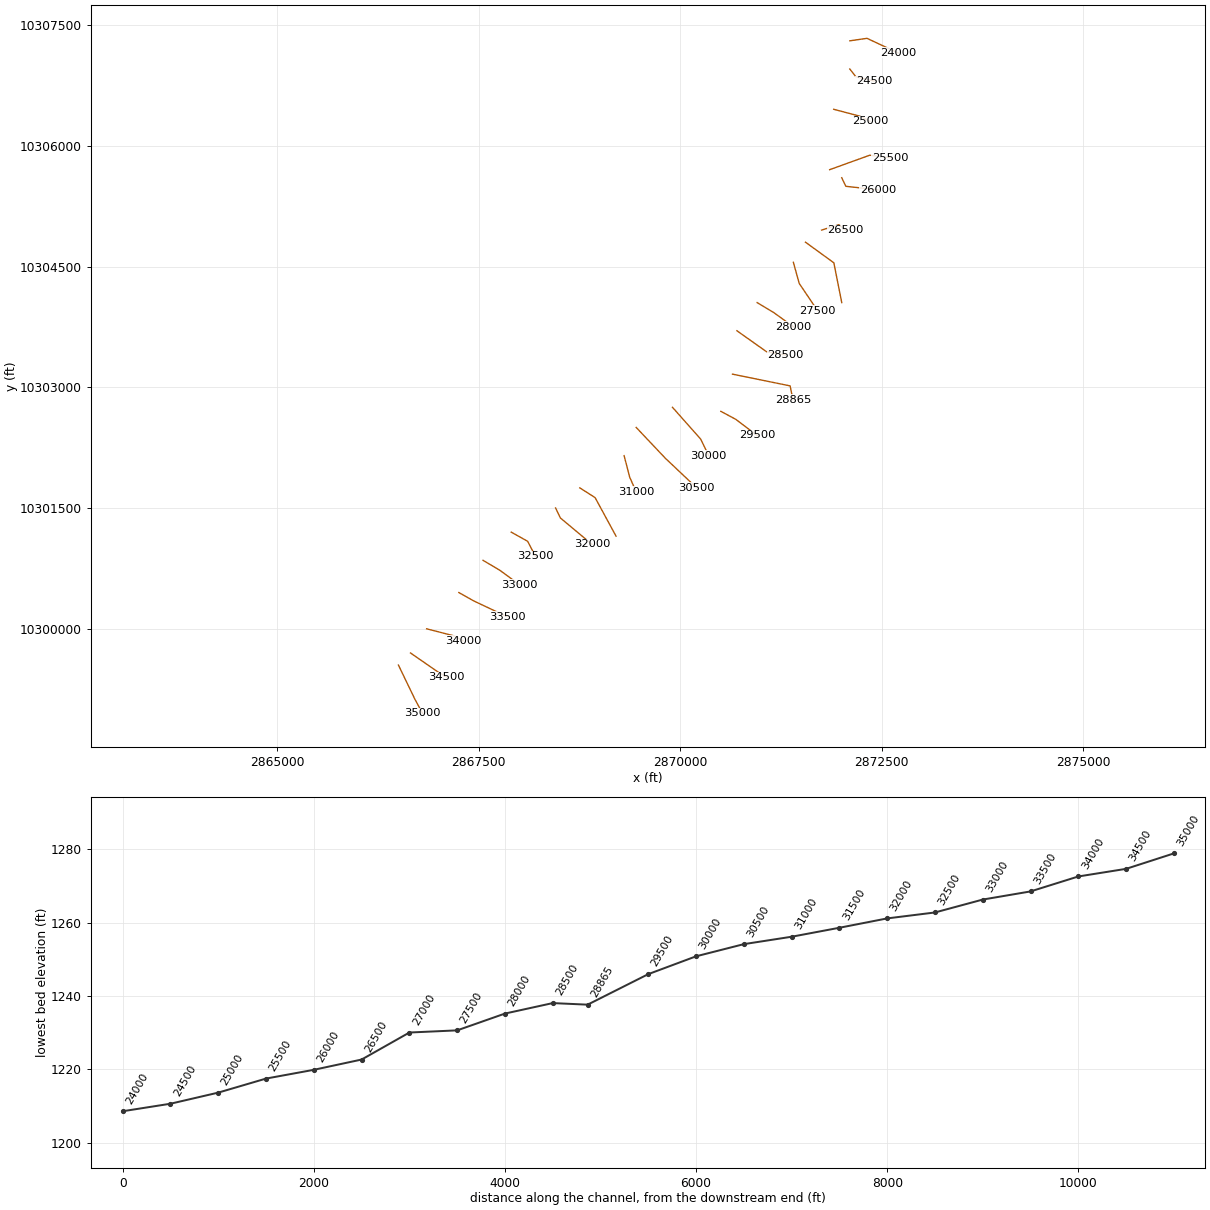
HEC-RAS study FALL CREEK.prj: FALL CREEK Base Level Engineering

--- FALL CREEK.g01 (geometry) --- (continued)

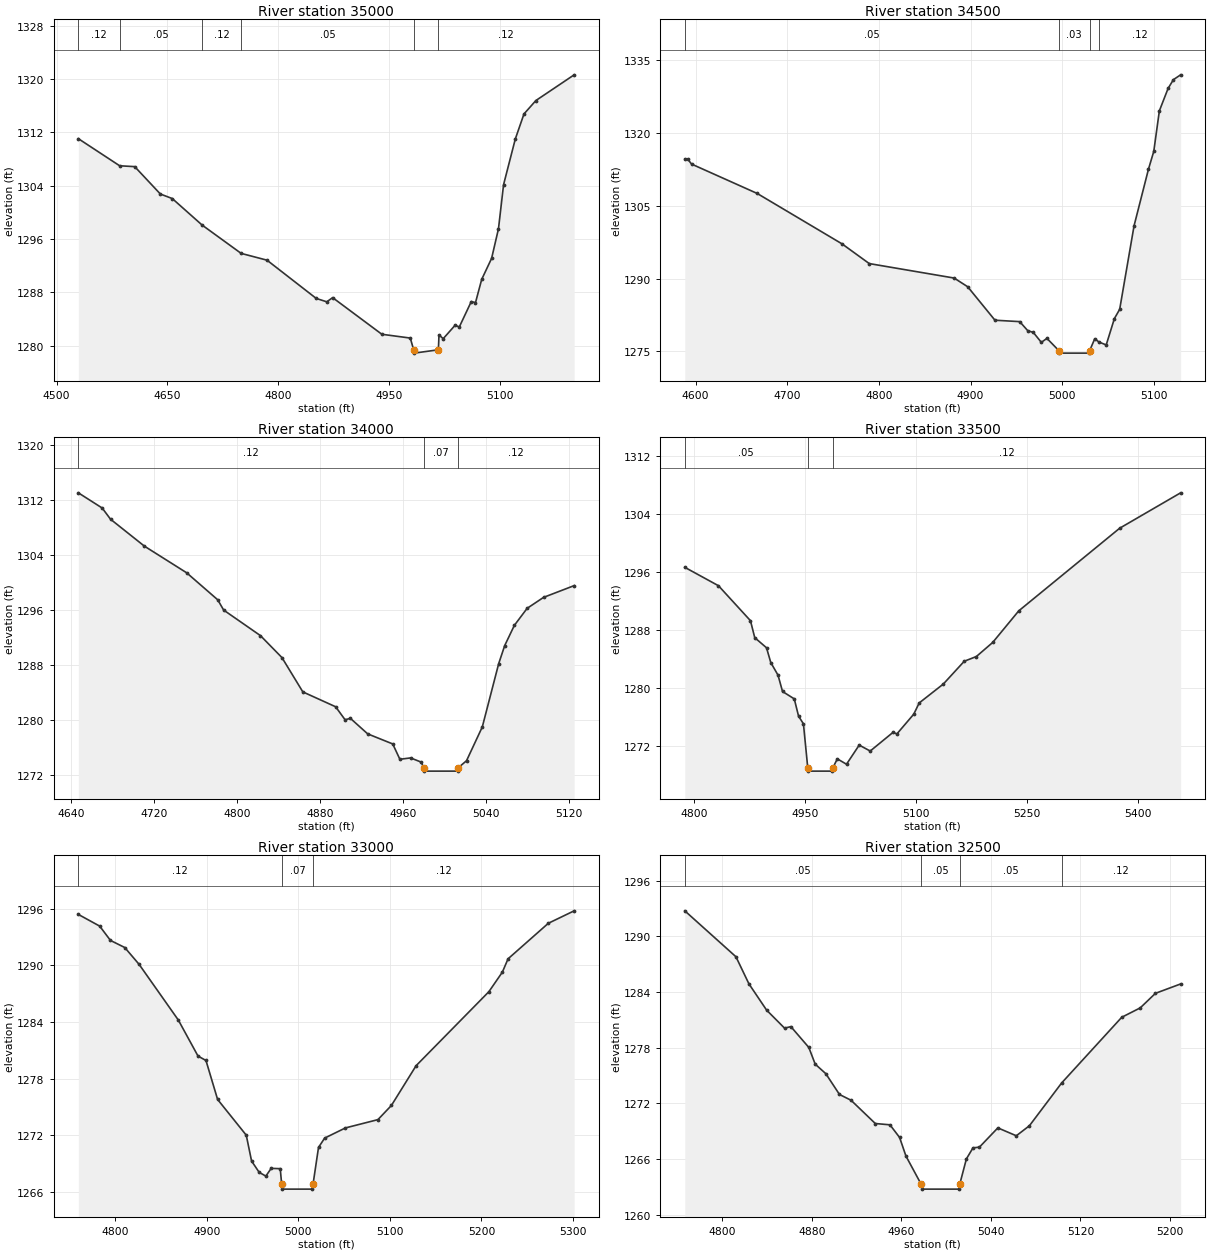
Type RM Length L Ch R = 1 ,35000   ,500,500,500
BEGIN DESCRIPTION:
FALL CREEK 70.0
END DESCRIPTION:
XS GIS Cut Line= 3
      2866505.71     10299553.07      2866710.08     10299129.27
      2866805.67     10298953.14
#Sta/Elev= 30
  4529.5 1311.05  4585.4 1306.98  4605.8 1306.85  4640.5 1302.74  4656.6 1302.06
    4697 1298.08  4749.8 1293.83  4784.8 1292.81  4851.4 1287.07  4865.7 1286.56
  4873.6 1287.19  4940.2 1281.69  4978.7 1281.12  4983.2 1279.36  4983.8 1278.86
  5016.7 1279.36  5017.5  1281.6  5023.2 1281.03  5039.3 1283.04    5045 1282.79
  5061.2  1286.6  5066.9 1286.44  5075.3 1289.93  5088.7 1293.08    5098 1297.53
  5104.9 1304.15  5120.8 1311.01  5132.5 1314.76  5148.6 1316.77  5200.4 1320.63
#Mann= 6 ,-1 , 0
  4529.5     .12       0  4585.4     .05       0    4697     .12       0
  4749.8     .05       0  4983.2     .05       0  5016.7     .12       0
Bank Sta=4983.2,5016.7
XS Rating Curve= 0 ,0
Exp/Cntr=0.3,0.1

Type RM Length L Ch R = 1 ,34500   ,500,500,500
BEGIN DESCRIPTION:
FALL CREEK 69.0
END DESCRIPTION:
XS GIS Cut Line= 3
      2866655.72     10299703.09      2866994.25     10299468.62
      2867105.72     10299403.09
#Sta/Elev= 30
  4588.2 1314.66  4591.2 1314.66  4595.6  1313.6  4667.2 1307.55  4759.8 1297.16
  4789.5  1293.1  4882.1 1290.12  4896.9 1288.33  4926.7 1281.43  4953.7 1281.14
  4962.5 1279.27  4968.5 1278.92  4977.3 1276.87  4983.4 1277.69  4996.5 1275.15
  4997.1 1274.65  5029.4 1274.65    5030 1275.15  5035.6 1277.62  5040.2 1276.93
  5048.1 1276.34    5057 1281.76  5062.8 1283.68  5078.5  1300.9  5094.2 1312.54
    5100 1316.22  5106.1 1324.57  5115.6 1329.18  5121.4 1330.99  5129.3 1331.99
#Mann= 4 ,-1 , 0
  4588.2     .05       0  4996.5     .03       0    5030     .05       0
  5040.2     .12       0
Bank Sta=4996.5,5030
XS Rating Curve= 0 ,0
Exp/Cntr=0.3,0.1

Type RM Length L Ch R = 1 ,34000   ,500,500,500
BEGIN DESCRIPTION:
FALL CREEK 68.0
END DESCRIPTION:
XS GIS Cut Line= 3
      2866855.64     10300003.12      2867197.21     10299915.25
      2867305.68     10299853.12
#Sta/Elev= 30
  4647.3    1313  4670.3 1310.79  4678.3 1309.17    4711 1305.25  4751.7 1301.38
  4781.6 1297.46  4787.3 1295.97  4822.8 1292.25  4843.5 1289.06  4863.6 1284.08
  4895.2 1281.92  4904.3 1280.03  4909.4 1280.24  4926.1 1277.98  4950.2 1276.52
  4957.1 1274.29  4967.4 1274.49  4977.8 1273.87  4979.9 1273.07  4980.5 1272.57
  5012.8 1272.57  5013.4 1273.07  5021.3 1274.08  5036.5 1278.99  5052.3 1288.19
  5058.1 1290.81  5067.4 1293.75  5079.7 1296.22  5095.5 1297.81    5125 1299.52
#Mann= 3 ,-1 , 0
  4647.3     .12       0  4979.9     .07       0  5013.4     .12       0
Bank Sta=4979.9,5013.4
XS Rating Curve= 0 ,0
Exp/Cntr=0.3,0.1

Type RM Length L Ch R = 1 ,33500   ,500,500,500
BEGIN DESCRIPTION:
FALL CREEK 67.0
END DESCRIPTION:
XS GIS Cut Line= 3
      2867255.68     10300453.11      2867441.27      10300348.8
      2867855.69     10300153.11
#Sta/Elev= 30
  4787.1 1296.59  4832.7 1294.05    4876 1289.23  4881.8 1286.89  4897.7  1285.5
  4903.5 1283.46  4913.3 1281.72  4919.4 1279.47  4935.3 1278.45  4941.1 1276.07
  4947.7 1275.01  4953.5 1268.99  4954.2 1268.49    4987 1268.49  4987.7 1268.99
  4993.6 1270.18    5006 1269.44  5023.2 1272.08  5038.1 1271.26  5068.8 1273.82
  5074.3 1273.63  5097.1 1276.35  5104.4 1277.89  5137.1  1280.5  5165.4 1283.64
  5181.8 1284.29  5203.9 1286.23  5239.2 1290.59  5375.8 1301.98  5458.3 1306.86
#Mann= 3 ,-1 , 0
  4787.1     .05       0  4953.5     .07       0  4987.7     .12       0
Bank Sta=4953.5,4987.7
XS Rating Curve= 0 ,0
Exp/Cntr=0.3,0.1

Type RM Length L Ch R = 1 ,33000   ,500,500,500
BEGIN DESCRIPTION:
FALL CREEK 66.0
END DESCRIPTION:
XS GIS Cut Line= 3
      2867555.67     10300853.12      2867762.53     10300730.84
       2868005.7      10300553.1
#Sta/Elev= 30
  4759.7  1295.4    4783 1294.16  4794.8 1292.64  4810.4 1291.89  4826.1  1290.1
  4868.9  1284.2  4890.4 1280.38  4899.1 1279.91  4911.8 1275.78  4943.1 1271.99
  4948.9 1269.25  4957.2 1268.05  4964.5 1267.65  4970.3 1268.47  4980.2 1268.44
  4981.8 1266.77  4982.5 1266.27  5015.3 1266.27    5016 1266.77    5022 1270.69
  5028.7 1271.68  5051.4 1272.76  5086.9 1273.64  5101.6 1275.14  5128.6 1279.36
  5208.1 1287.21  5222.8 1289.28    5229 1290.69    5273 1294.46  5301.2 1295.78
#Mann= 3 ,-1 , 0
  4759.7     .12       0  4981.8     .07       0    5016     .12       0
Bank Sta=4981.8,5016
XS Rating Curve= 0 ,0
Exp/Cntr=0.3,0.1

Type RM Length L Ch R = 1 ,32500   ,500,500,500
BEGIN DESCRIPTION:
FALL CREEK 65.0
END DESCRIPTION:
XS GIS Cut Line= 3
      2867905.69     10301203.11      2868109.53     10301089.22
      2868205.69     10300903.09
#Sta/Elev= 30
  4766.5 1292.74  4812.2 1287.79  4823.8 1284.87  4839.6 1282.04  4855.6  1280.1
  4861.3 1280.26  4877.3 1278.02    4883 1276.22  4892.5 1275.19  4904.7 1272.95
    4915 1272.33  4936.7 1269.82  4949.8 1269.68  4958.4 1268.32  4964.1 1266.31
  4977.8 1263.25  4978.5 1262.75  5011.4 1262.75  5012.1 1263.25  5018.1 1266.01
    5024  1267.2  5029.7 1267.27  5046.2 1269.35  5062.7  1268.5  5074.4 1269.58
  5103.2 1274.19  5156.9 1281.27  5173.4 1282.28    5187 1283.85  5209.5 1284.86
#Mann= 4 ,-1 , 0
  4766.5     .05       0  4977.8     .05       0  5012.1     .05       0
  5103.2     .12       0
Bank Sta=4977.8,5012.1
XS Rating Curve= 0 ,0
Exp/Cntr=0.3,0.1

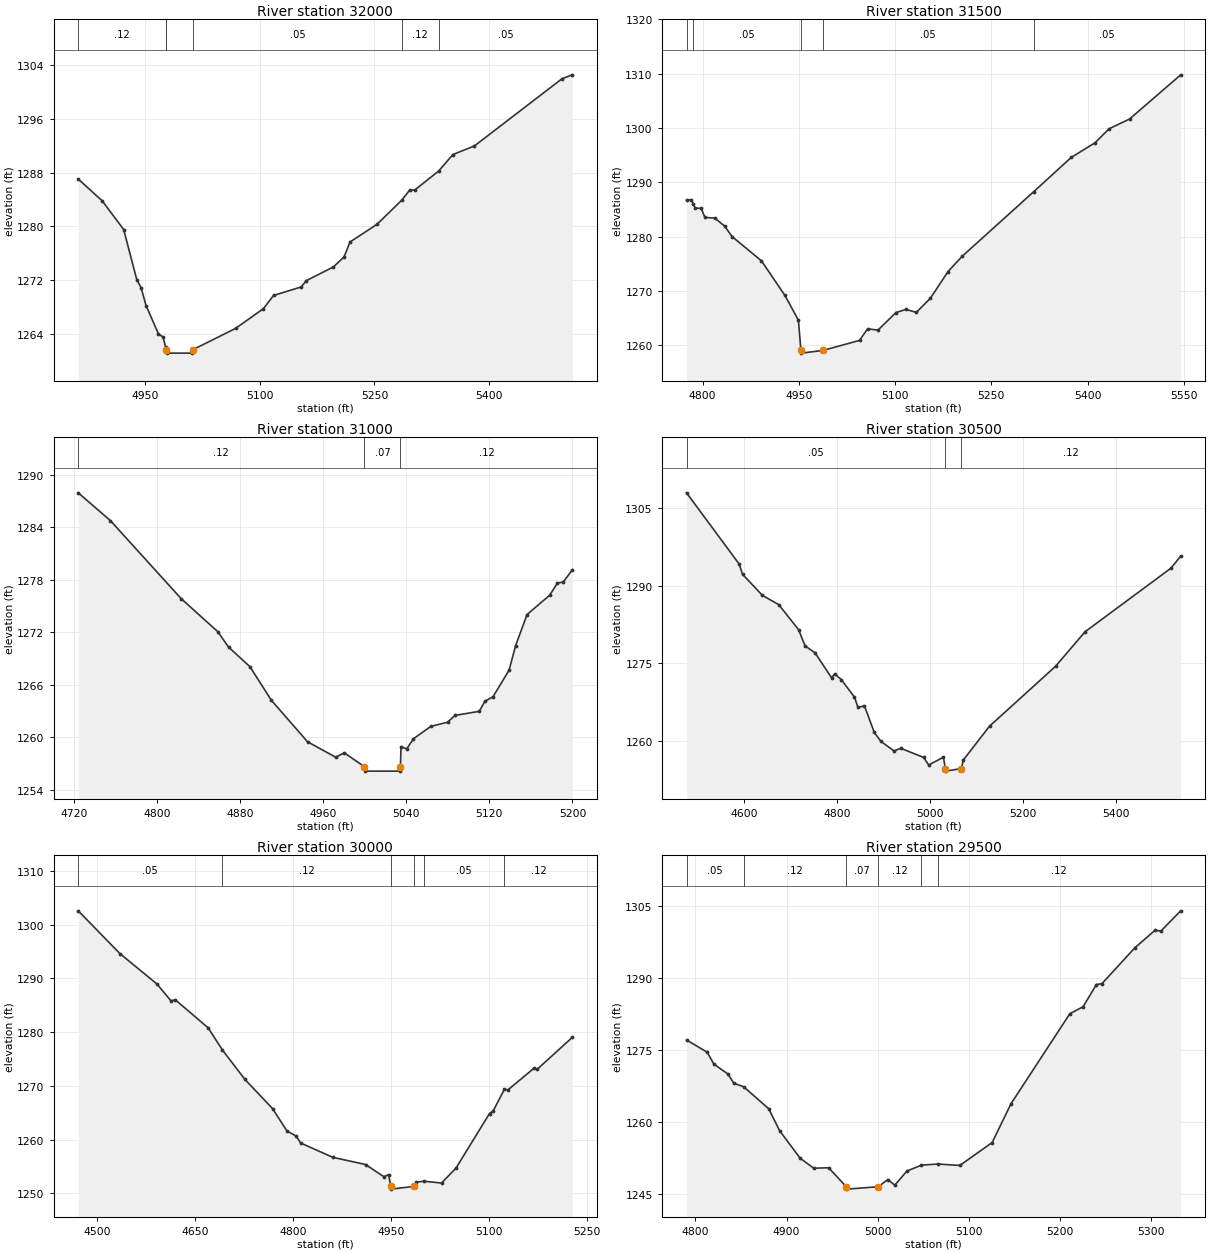
Type RM Length L Ch R = 1 ,32000   ,500,500,500
BEGIN DESCRIPTION:
FALL CREEK 64.0
END DESCRIPTION:
XS GIS Cut Line= 3
      2868455.68     10301503.12      2868515.01      10301379.3
      2868905.65     10301053.14
#Sta/Elev= 30
  4862.7 1287.05  4893.9 1283.83  4922.1 1279.54  4939.2 1272.09  4944.8 1270.89
  4951.4 1268.21  4967.5 1264.02  4973.6 1263.52  4977.1 1261.98  4977.9 1261.63
  4978.6 1261.13  5011.6 1261.13  5012.4 1261.63  5068.4 1264.81  5104.8 1267.75
  5118.1 1269.72  5154.3 1270.99  5160.8 1271.92  5196.3 1273.96  5210.3 1275.46
  5218.1 1277.69  5253.2  1280.3  5286.1 1283.95  5296.2 1285.43  5302.7 1285.42
  5333.9 1288.24  5352.6 1290.71  5380.8 1291.99  5495.3    1302  5508.9 1302.58
#Mann= 6 ,-1 , 0
  4862.7     .12       0  4977.1     .05       0  4977.9     .05       0
  5012.4     .05       0  5286.1     .12       0  5333.9     .05       0
Bank Sta=4977.9,5012.4
XS Rating Curve= 0 ,0
Exp/Cntr=0.3,0.1

Type RM Length L Ch R = 1 ,31500   ,500,500,500
BEGIN DESCRIPTION:
FALL CREEK 63.0
END DESCRIPTION:
XS GIS Cut Line= 3
      2868755.72     10301753.09      2868945.59     10301632.19
      2869205.67     10301153.13
#Sta/Elev= 30
  4774.9 1286.73  4782.5 1286.79  4785.4 1286.04  4788.4 1285.27  4797.7  1285.2
  4803.6 1283.53  4818.9 1283.42  4834.1 1281.96    4846 1280.01  4891.7 1275.55
  4928.1 1269.22  4949.2 1264.66  4953.2 1259.08  4953.9 1258.58  4987.7 1259.08
  5044.5 1260.92  5057.1 1263.05  5073.2 1262.81  5101.4 1266.05  5116.9 1266.62
  5133.1 1266.07    5155 1268.68  5182.5 1273.59  5204.4 1276.38  5315.7 1288.24
  5374.4 1294.57  5411.6 1297.27  5433.4 1299.84  5465.5 1301.65  5545.1 1309.77
#Mann= 5 ,-1 , 0
  4774.9     .12       0  4785.4     .05       0  4953.2     .07       0
  4987.7     .05       0  5315.7     .05       0
Bank Sta=4953.2,4987.7
XS Rating Curve= 0 ,0
Exp/Cntr=0.3,0.1

Type RM Length L Ch R = 1 ,31000   ,500,500,500
BEGIN DESCRIPTION:
FALL CREEK 62.0
END DESCRIPTION:
XS GIS Cut Line= 3
      2869305.68     10302153.14      2869374.79     10301886.03
      2869455.68     10301703.12
#Sta/Elev= 30
  4724.1 1287.96  4755.1 1284.78  4823.1 1275.87  4858.4 1272.09  4868.9 1270.31
  4889.4 1268.08  4910.1 1264.23  4944.9 1259.49    4972 1257.72  4980.4 1258.22
  4999.7 1256.63  5000.5 1256.13  5033.7 1256.13  5034.4 1256.63  5034.9 1258.93
  5040.4 1258.67  5046.9 1259.83  5063.7 1261.25  5079.7 1261.72    5087  1262.5
  5110.3 1262.97  5115.7 1264.12  5123.5 1264.63    5139 1267.68  5145.3 1270.48
  5156.3 1274.04  5178.1 1276.25  5185.6 1277.64  5191.1 1277.75    5200 1279.17
#Mann= 3 ,-1 , 0
  4724.1     .12       0  4999.7     .07       0  5034.4     .12       0
Bank Sta=4999.7,5034.4
XS Rating Curve= 0 ,0
Exp/Cntr=0.3,0.1

Type RM Length L Ch R = 1 ,30500   ,500,500,500
BEGIN DESCRIPTION:
FALL CREEK 61.0
END DESCRIPTION:
XS GIS Cut Line= 3
      2869455.72     10302503.08      2869814.84       10302123.
      2870205.67     10301753.13
#Sta/Elev= 30
  4477.1    1308  4590.1 1294.21  4597.4 1292.22  4639.9 1288.15  4675.1 1286.35
  4717.6 1281.51  4731.7 1278.35  4752.8 1277.05  4788.4 1272.19  4795.2 1272.94
  4809.4 1271.83  4837.7 1268.44    4845  1266.5  4859.1 1266.72  4880.2 1261.62
  4894.3 1259.88  4922.7 1258.01  4936.8 1258.54  4986.2 1256.76    4997  1255.3
  5028.7 1256.81  5032.7 1254.61  5033.5 1254.11  5067.4 1254.61  5071.1 1256.24
  5127.7 1262.82  5269.3  1274.4  5332.8  1281.1  5516.9 1293.39  5538.1 1295.74
#Mann= 3 ,-1 , 0
  4477.1     .05       0  5032.7     .05       0  5067.4     .12       0
Bank Sta=5032.7,5067.4
XS Rating Curve= 0 ,0
Exp/Cntr=0.3,0.1

Type RM Length L Ch R = 1 ,30000   ,500,500,500
BEGIN DESCRIPTION:
FALL CREEK 60.0
END DESCRIPTION:
XS GIS Cut Line= 3
      2869905.67     10302753.12      2870256.04     10302357.72
      2870355.69     10302153.09
#Sta/Elev= 30
  4471.7 1302.57  4535.7 1294.58    4592 1288.97  4613.5 1285.83  4620.2 1286.01
  4670.4  1280.8  4692.1  1276.7  4726.4 1271.24    4769 1265.76  4790.8 1261.63
    4805 1260.66  4811.7 1259.38    4861 1256.71  4911.2 1255.37  4939.3 1253.09
  4946.4 1253.49  4949.8 1251.29  4950.6 1250.79  4984.7 1251.29    4989  1252.1
  5000.6 1252.26  5027.4 1251.92  5049.6 1254.72  5100.8 1264.86  5106.4 1265.35
  5123.5 1269.35  5128.9 1269.25  5168.4 1273.24    5174 1273.12  5227.6 1279.04
#Mann= 6 ,-1 , 0
  4471.7     .05       0  4692.1     .12       0  4949.8     .07       0
  4984.7     .12       0  5000.6     .05       0  5123.5     .12       0
Bank Sta=4949.8,4984.7
XS Rating Curve= 0 ,0
Exp/Cntr=0.3,0.1

Type RM Length L Ch R = 1 ,29500   ,635,635,635
BEGIN DESCRIPTION:
FALL CREEK 59.0
END DESCRIPTION:
XS GIS Cut Line= 3
      2870505.71      10302703.1      2870690.67     10302604.08
      2870955.69     10302403.11
#Sta/Elev= 30
  4790.2 1277.04  4812.9 1274.48  4820.2    1272  4835.5 1269.96  4842.2    1268
  4852.8 1267.29  4880.4  1262.7  4892.3 1258.14  4914.9 1252.37  4929.9 1250.29
  4946.2 1250.39  4965.5 1246.43  4966.3 1245.93  5000.5 1246.43  5011.2 1247.93
  5018.8 1246.75    5032 1249.69    5048 1250.93  5065.8 1251.16  5090.2 1250.87
  5125.6 1255.64  5146.4 1263.76  5210.9 1282.51  5225.5 1283.97    5240 1288.58
  5246.3 1288.81  5282.4 1296.29  5304.5 1299.92  5310.8 1299.74  5332.6 1303.97
#Mann= 6 ,-1 , 0
  4790.2     .05       0  4852.8     .12       0  4965.5     .07       0
  5000.5     .12       0    5048     .05       0  5065.8     .12       0
Bank Sta=4965.5,5000.5
XS Rating Curve= 0 ,0
Exp/Cntr=0.3,0.1

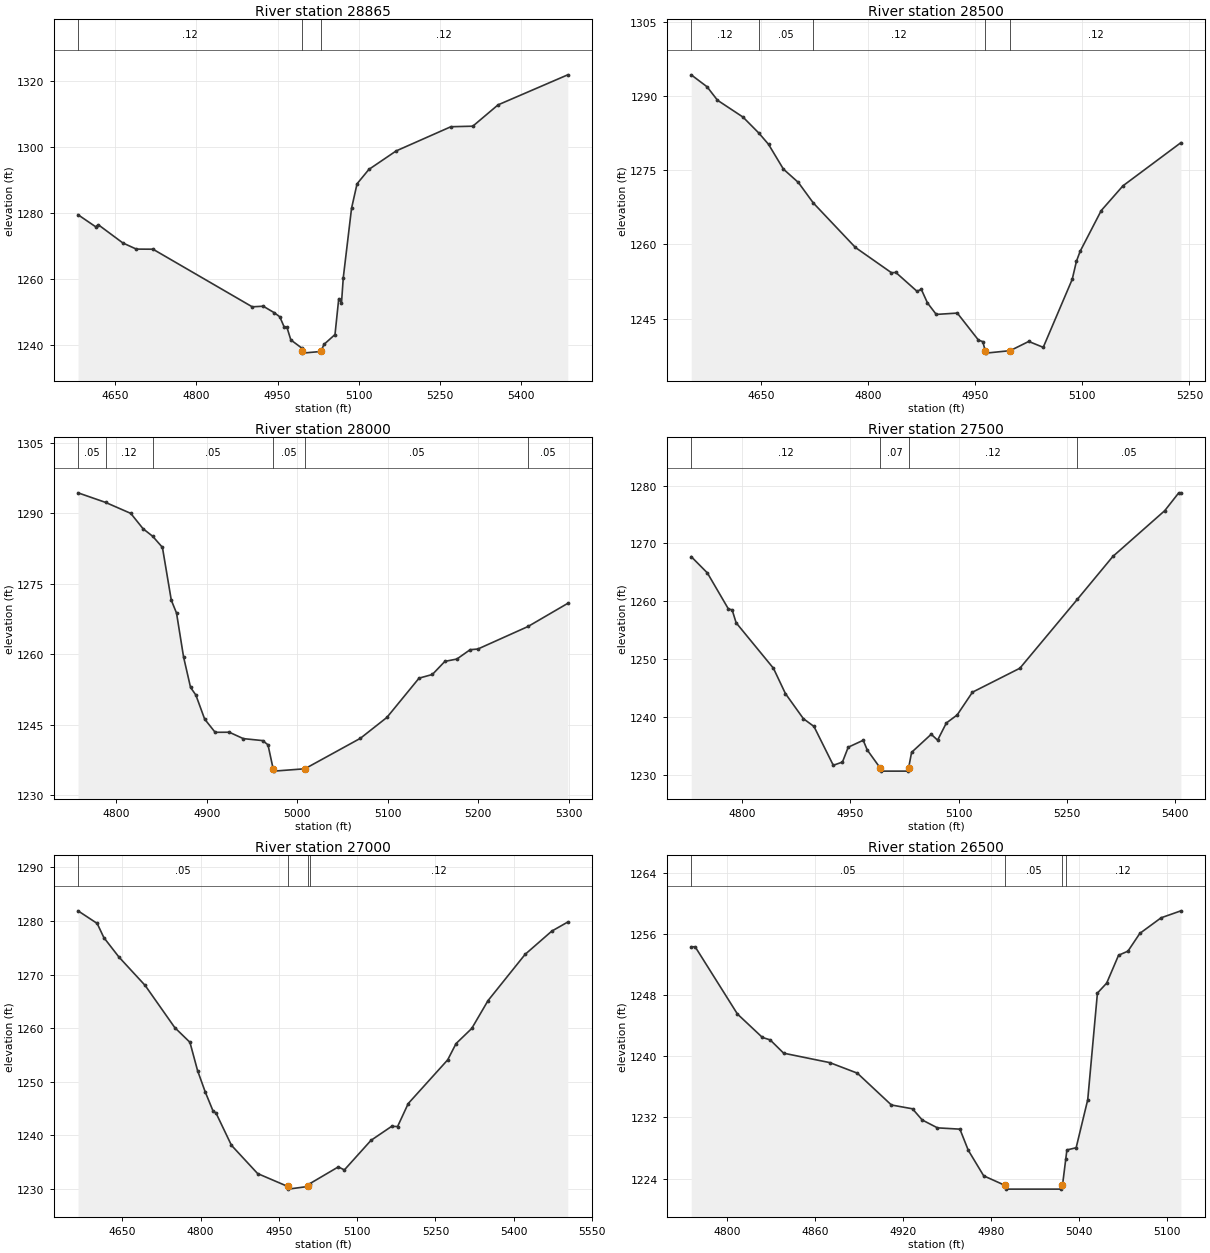
Type RM Length L Ch R = 1 ,28865   ,365,365,365
BEGIN DESCRIPTION:
Mapping XS 0980be57
END DESCRIPTION:
XS GIS Cut Line= 3
       2870650.1     10303164.81      2871365.36     10303018.98
       2871399.8     10302846.76
#Sta/Elev= 30
  4581.1 1279.52  4613.5  1275.9  4618.6 1276.49    4664 1270.97  4688.9 1269.11
  4719.7 1269.08  4903.2 1251.63  4923.6 1251.81    4944 1249.84  4954.2  1248.6
  4962.2 1245.56  4967.3 1245.47  4974.6 1241.61    4995 1239.11  4995.2  1238.1
    4996  1237.6  5030.2  1238.1  5035.9 1240.24  5056.3 1243.23  5063.2 1254.09
  5068.3 1252.77  5071.6 1260.45  5086.9 1281.48  5097.1  1288.9  5118.9 1293.24
  5169.4 1298.85  5270.6 1306.18  5311.1 1306.34  5357.8  1312.8  5486.7  1321.9
#Mann= 3 ,-1 , 0
  4581.1     .12       0  4995.2     .07       0  5030.2     .12       0
Bank Sta=4995.2,5030.2
XS Rating Curve= 0 ,0
Exp/Cntr=0.3,0.1

Type RM Length L Ch R = 1 ,28500   ,500,500,500
BEGIN DESCRIPTION:
FALL CREEK 57.0
END DESCRIPTION:
XS GIS Cut Line= 3
      2870705.67     10303703.12      2871071.25     10303444.01
      2871305.71     10303403.11
#Sta/Elev= 30
  4551.9 1294.25  4574.1 1291.84  4588.7 1289.12  4624.5 1285.71  4646.7 1282.48
  4660.2 1280.22  4681.1  1275.2    4702 1272.51    4723 1268.36    4782 1259.37
  4832.5 1254.27  4838.6 1254.33  4868.2 1250.53  4874.3 1250.91  4882.9 1248.17
  4895.2 1245.85  4924.7 1246.12  4954.3 1240.67  4960.4 1240.35  4963.8 1238.53
  4964.6 1238.03  4998.8 1238.53  5024.8 1240.39  5045.1  1239.2  5085.7 1252.94
  5091.6 1256.58  5096.7 1258.57  5126.3 1266.82  5156.8 1271.83    5238 1280.55
#Mann= 5 ,-1 , 0
  4551.9     .12       0  4646.7     .05       0    4723     .12       0
  4963.8     .07       0  4998.8     .12       0
Bank Sta=4963.8,4998.8
XS Rating Curve= 0 ,0
Exp/Cntr=0.3,0.1

Type RM Length L Ch R = 1 ,28000   ,500,500,500
BEGIN DESCRIPTION:
FALL CREEK 56.0
END DESCRIPTION:
XS GIS Cut Line= 3
      2870955.65     10304053.13       2871163.6     10303928.37
      2871405.71     10303753.09
#Sta/Elev= 30
  4757.5 1294.32    4788 1292.28  4815.8 1289.95  4829.5 1286.67    4840 1285.09
  4850.8 1282.73  4860.6 1271.51  4866.4 1268.76  4874.2 1259.41  4881.9 1252.96
  4887.8 1251.33  4897.5 1246.22  4909.1 1243.42  4924.7 1243.44  4940.2 1242.08
  4961.6 1241.66  4967.5 1240.76  4973.2 1235.67    4974 1235.17  5008.3 1235.67
  5069.6 1242.14    5099 1246.59  5134.5 1254.93  5149.2 1255.71  5163.1  1258.5
  5176.3 1258.99    5191 1260.98  5199.5 1261.12    5255 1265.91  5298.9 1270.83
#Mann= 6 ,-1 , 0
  4757.5     .05       0    4788     .12       0    4840     .05       0
  4973.2     .05       0  5008.3     .05       0    5255     .05       0
Bank Sta=4973.2,5008.3
XS Rating Curve= 0 ,0
Exp/Cntr=0.3,0.1

Type RM Length L Ch R = 1 ,27500   ,500,500,500
BEGIN DESCRIPTION:
FALL CREEK 55.0
END DESCRIPTION:
XS GIS Cut Line= 3
      2871405.68     10304553.13      2871477.66     10304291.96
      2871705.67     10303953.14
#Sta/Elev= 30
  4729.1 1267.72  4751.5  1264.9  4780.7 1258.66  4785.9  1258.5  4791.4 1256.27
  4843.2 1248.39  4859.8 1244.01  4884.7 1239.67  4899.4 1238.32  4926.2  1231.6
  4938.9 1232.16  4946.9 1234.73  4967.7 1235.93  4973.3 1234.25  4991.5 1231.09
  4992.5 1230.59  5029.6 1230.59  5030.6 1231.09  5034.8 1233.84    5062 1236.97
  5070.9 1235.95    5083 1238.92    5098 1240.31  5119.2 1244.25    5185  1248.4
  5264.6 1260.31    5314 1267.75    5386 1275.68  5405.4 1278.76  5408.4 1278.76
#Mann= 4 ,-1 , 0
  4729.1     .12       0  4991.5     .07       0  5030.6     .12       0
  5264.6     .05       0
Bank Sta=4991.5,5030.6
XS Rating Curve= 0 ,0
Exp/Cntr=0.3,0.1

Type RM Length L Ch R = 1 ,27000   ,500,500,500
BEGIN DESCRIPTION:
FALL CREEK 54.0
END DESCRIPTION:
XS GIS Cut Line= 3
      2871555.68     10304803.11      2871907.56     10304547.19
      2872005.68     10304053.14
#Sta/Elev= 30
  4564.9 1281.87  4601.6 1279.52  4614.4 1276.88  4643.3 1273.26  4693.6 1267.96
  4750.4  1260.1  4779.4 1257.37    4794 1252.11  4808.7 1248.13  4823.4 1244.64
  4829.6 1244.15    4859 1238.17  4909.2  1232.9  4966.9  1230.5  4967.9    1230
    5006  1230.5  5008.7 1230.99  5063.8 1234.14  5075.5 1233.58  5126.5 1239.09
  5166.1  1241.7  5177.5 1241.67  5197.9 1245.95  5273.5 1254.09  5289.6 1257.13
  5319.6 1259.94  5350.8 1265.13  5421.9 1273.75  5473.1 1278.09  5503.7 1279.78
#Mann= 4 ,-1 , 0
  4564.9     .05       0  4966.9     .05       0    5006     .05       0
  5008.7     .12       0
Bank Sta=4966.9,5006
XS Rating Curve= 0 ,0
Exp/Cntr=0.3,0.1

Type RM Length L Ch R = 1 ,26500   ,500,500,500
BEGIN DESCRIPTION:
FALL CREEK 53.0
END DESCRIPTION:
XS GIS Cut Line= 3
      2871755.64      10304953.1      2871969.43     10305020.63
      2872055.65     10304953.14
#Sta/Elev= 30
  4775.8 1254.31  4778.5 1254.31  4807.3 1245.52  4824.3 1242.46  4829.6 1242.14
  4838.8  1240.4  4870.2 1239.17    4889 1237.79  4912.2 1233.63  4926.6 1233.13
  4933.2 1231.67  4943.6 1230.64  4958.9 1230.47  4964.6 1227.71  4975.1 1224.37
  4989.5 1223.13  4990.5 1222.63  5027.8 1222.63  5028.8 1223.13    5031 1226.52
  5031.8 1227.75  5038.1 1228.04    5046 1234.32  5052.6 1248.26  5058.9 1249.56
    5067  1253.2  5073.4 1253.74  5081.5 1256.06    5096  1258.1  5109.5 1259.01
#Mann= 4 ,-1 , 0
  4775.8     .05       0  4989.5     .05       0  5028.8     .05       0
    5031     .12       0
Bank Sta=4989.5,5028.8
XS Rating Curve= 0 ,0
Exp/Cntr=0.3,0.1

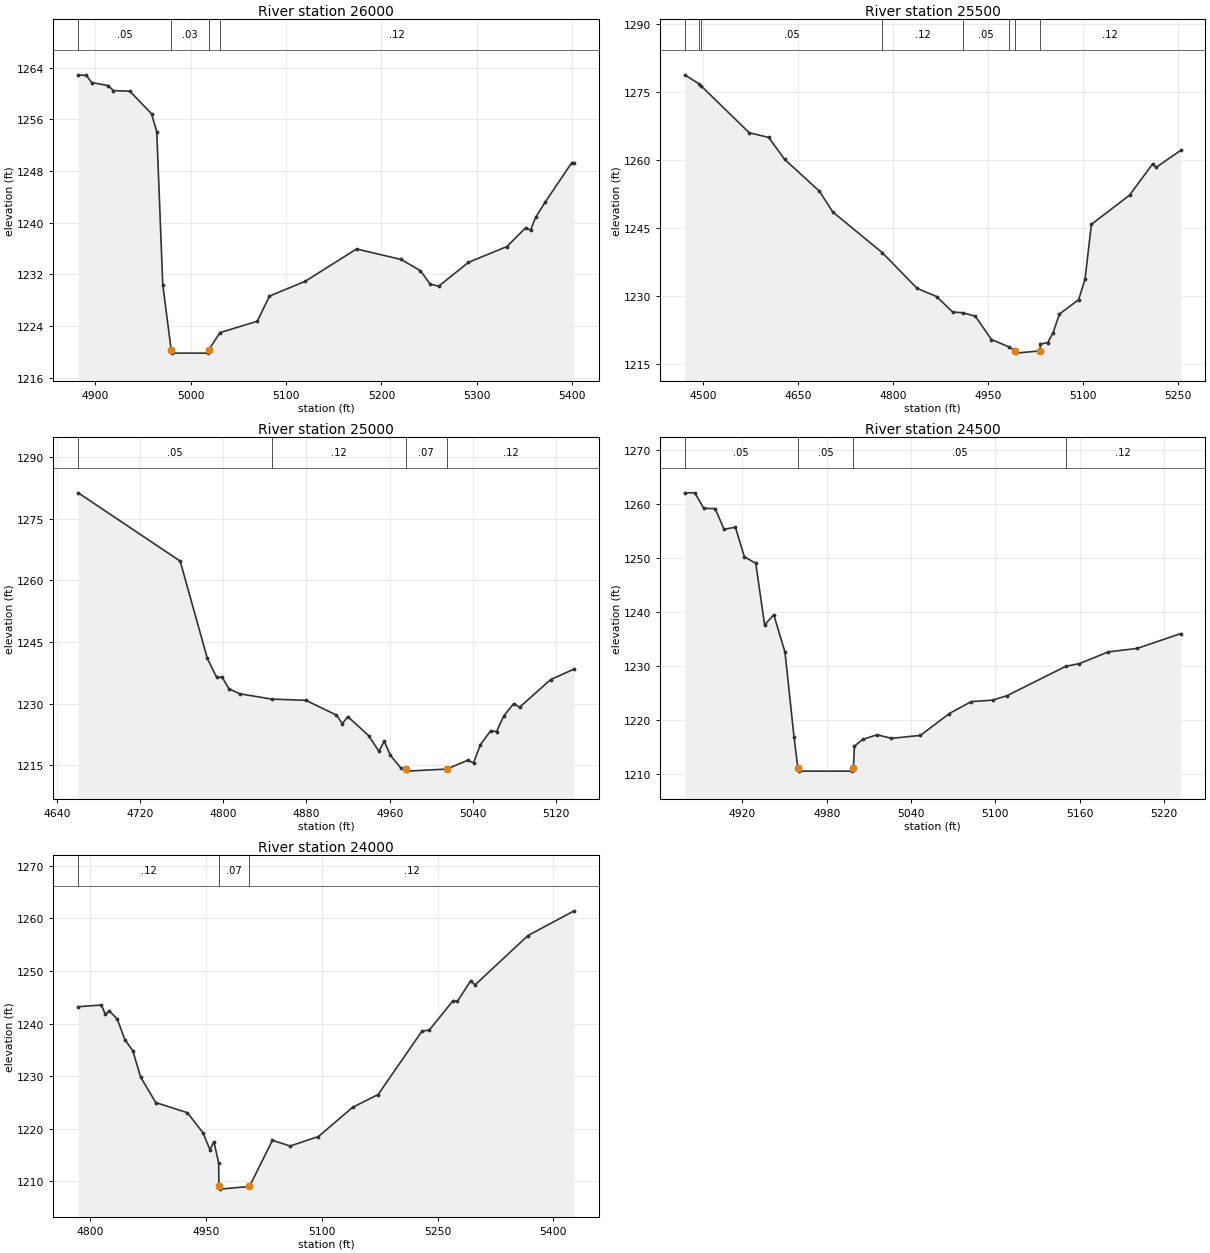
Type RM Length L Ch R = 1 ,26000   ,500,500,500
BEGIN DESCRIPTION:
FALL CREEK 52.0
END DESCRIPTION:
XS GIS Cut Line= 3
      2872005.66     10305603.15       2872056.2     10305496.85
      2872455.71     10305453.11
#Sta/Elev= 30
  4882.3  1262.9  4890.9  1262.8  4896.5  1261.7  4913.7 1261.23  4919.2 1260.46
  4936.4 1260.37  4959.1 1256.88  4964.6 1254.09  4970.9  1230.4  4979.7 1220.33
  4980.7 1219.83    5018 1219.83    5019 1220.33  5030.8    1223  5069.9 1224.76
  5082.7 1228.66  5120.2 1230.95  5173.9 1235.95  5220.8 1234.32  5240.9 1232.58
    5251 1230.52    5260 1230.19  5291.2 1233.88  5331.5 1236.33  5351.2 1239.25
  5356.3 1238.87  5361.6 1240.86  5371.7 1243.23  5399.4  1249.3  5401.9  1249.3
#Mann= 4 ,-1 , 0
  4882.3     .05       0  4979.7     .03       0    5019     .05       0
  5030.8     .12       0
Bank Sta=4979.7,5019
XS Rating Curve= 0 ,0
Exp/Cntr=0.5,0.3

Type RM Length L Ch R = 1 ,25500   ,500,500,500
BEGIN DESCRIPTION:
FALL CREEK 51.0
END DESCRIPTION:
XS GIS Cut Line= 3
      2871855.72     10305703.13        2872353.     10305882.97
      2872605.64     10305853.12
#Sta/Elev= 30
  4471.2 1278.79  4493.6 1276.83  4496.6 1276.42  4573.1 1266.03  4603.8 1264.99
  4629.1 1260.15  4683.8 1253.17  4705.1 1248.56    4783 1239.62  4838.4 1231.71
    4869 1229.91  4894.4  1226.5  4910.6 1226.34  4930.3 1225.56  4955.7 1220.44
  4983.4 1218.81  4993.1 1217.94  4994.1 1217.44  5032.5 1217.94  5032.9 1219.43
  5044.7 1219.78  5053.1 1221.98  5063.1 1226.06  5093.3 1229.22  5103.4 1233.69
  5113.5 1245.83  5173.9 1252.28  5210.5 1259.21  5215.5 1258.38  5254.4 1262.12
#Mann= 8 ,-1 , 0
  4471.2     .05       0  4493.6     .12       0  4496.6     .05       0
    4783     .12       0  4910.6     .05       0  4983.4     .12       0
  4993.1     .07       0  5032.5     .12       0
#XS Ineff= 2 , 0
       0    4924                       0
Permanent Ineff=
       F       F
Bank Sta=4993.1,5032.5
XS Rating Curve= 0 ,0
Exp/Cntr=0.3,0.1

Type RM Length L Ch R = 1 ,25000   ,500,500,500
BEGIN DESCRIPTION:
FALL CREEK 50.0
END DESCRIPTION:
XS GIS Cut Line= 3
      2871905.71      10306453.1      2872233.86     10306366.43
      2872355.69     10306303.11
#Sta/Elev= 30
  4660.6 1281.26  4758.6 1264.66  4784.7 1241.01  4793.7 1236.39  4798.9 1236.47
  4805.4 1233.65  4815.7 1232.42  4846.6 1231.12  4879.4 1230.83  4908.8 1227.23
  4914.5 1225.16  4919.7 1226.87  4939.8 1222.23  4949.6 1218.43  4954.8  1220.9
  4960.5  1217.5  4970.9 1214.31  4975.3 1214.11  4976.3 1213.61  5014.8 1214.11
    5035 1216.25  5040.6 1215.61  5047.1 1220.01  5057.1 1223.43  5062.7 1223.22
  5069.7 1227.03  5079.2 1230.03  5084.8 1229.13  5114.8 1235.88  5137.3 1238.42
#Mann= 4 ,-1 , 0
  4660.6     .05       0  4846.6     .12       0  4975.3     .07       0
  5014.8     .12       0
Bank Sta=4975.3,5014.8
XS Rating Curve= 0 ,0
Exp/Cntr=0.3,0.1

Type RM Length L Ch R = 1 ,24500   ,500,500,500
BEGIN DESCRIPTION:
FALL CREEK 49.0
END DESCRIPTION:
XS GIS Cut Line= 3
       2872105.7     10306953.09      2872180.29     10306857.69
      2872405.68     10306803.11
#Sta/Elev= 30
  4878.9 1262.13  4886.1 1262.13  4892.5 1259.26  4900.6 1259.21  4906.9 1255.38
    4915 1255.76  4921.4 1250.27  4929.5 1249.08  4935.8 1237.64  4942.3 1239.55
  4950.3 1232.62  4956.7 1216.98  4959.5 1211.08  4960.5 1210.58    4998 1210.58
    4999 1211.08  4999.7 1215.19  5005.5 1216.44  5015.8 1217.31  5026.1 1216.66
  5046.7  1217.2  5067.3 1221.25  5082.9 1223.46  5098.1 1223.73  5108.4 1224.56
    5150 1229.98  5159.9  1230.5  5180.5 1232.67    5201 1233.31  5231.9 1236.05
#Mann= 4 ,-1 , 0
  4878.9     .05       0  4959.5     .05       0    4999     .05       0
    5150     .12       0
Bank Sta=4959.5,4999
XS Rating Curve= 0 ,0
Exp/Cntr=0.3,0.1

Type RM Length L Ch R = 1 ,24000   ,500,500,500
BEGIN DESCRIPTION:
FALL CREEK 48.0
END DESCRIPTION:
XS GIS Cut Line= 3
      2872105.69     10307303.11      2872318.87     10307333.93
      2872705.69     10307153.11
#Sta/Elev= 30
  4784.6  1243.2  4814.7 1243.52  4819.7 1241.73    4825 1242.38  4835.1 1240.88
  4845.2 1236.88  4855.3 1234.84  4865.4 1229.84    4885 1224.98  4926.1 1223.05
  4946.3 1219.22  4955.3 1216.02  4960.4 1217.54  4966.5  1213.5  4966.9 1209.03
  4967.9 1208.53  5006.4 1209.03  5036.2 1217.81  5059.1 1216.72  5095.8 1218.53
    5140 1224.07  5173.1 1226.51    5230 1238.58  5239.3 1238.74  5270.2 1244.36
  5275.7 1244.19  5293.1 1248.17  5298.6 1247.34  5367.1 1256.71    5427 1261.42
#Mann= 3 ,-1 , 0
  4784.6     .12       0  4966.9     .07       0  5006.4     .12       0
Bank Sta=4966.9,5006.4
XS Rating Curve= 0 ,0
Exp/Cntr=0.3,0.1