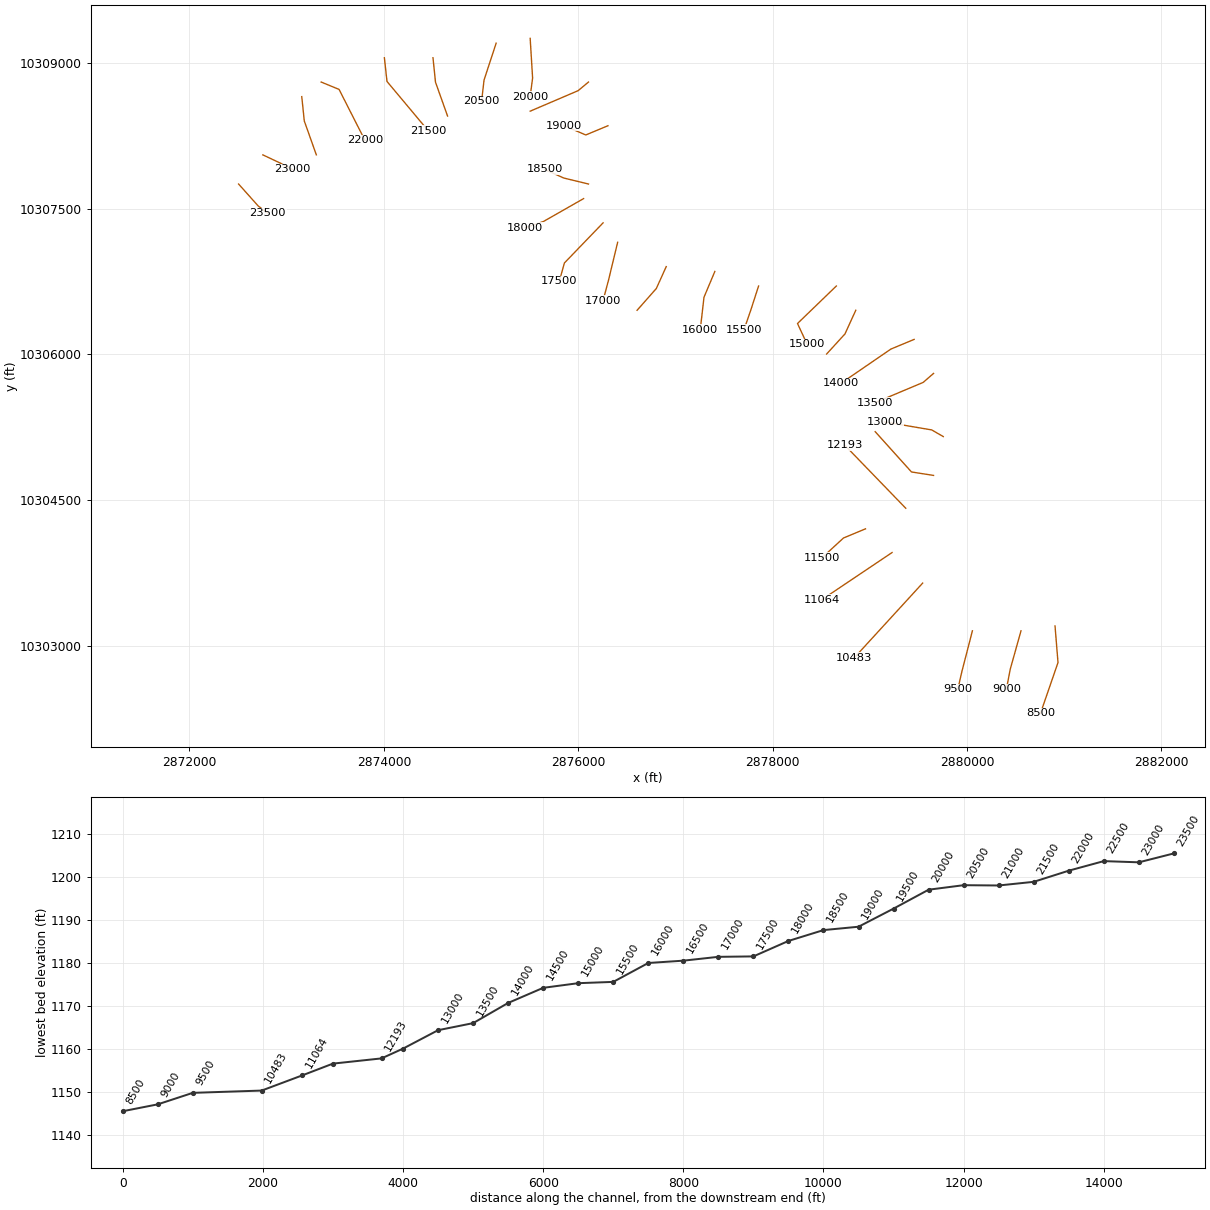
HEC-RAS study FALL CREEK.prj: FALL CREEK Base Level Engineering

--- FALL CREEK.g01 (geometry) --- (continued)

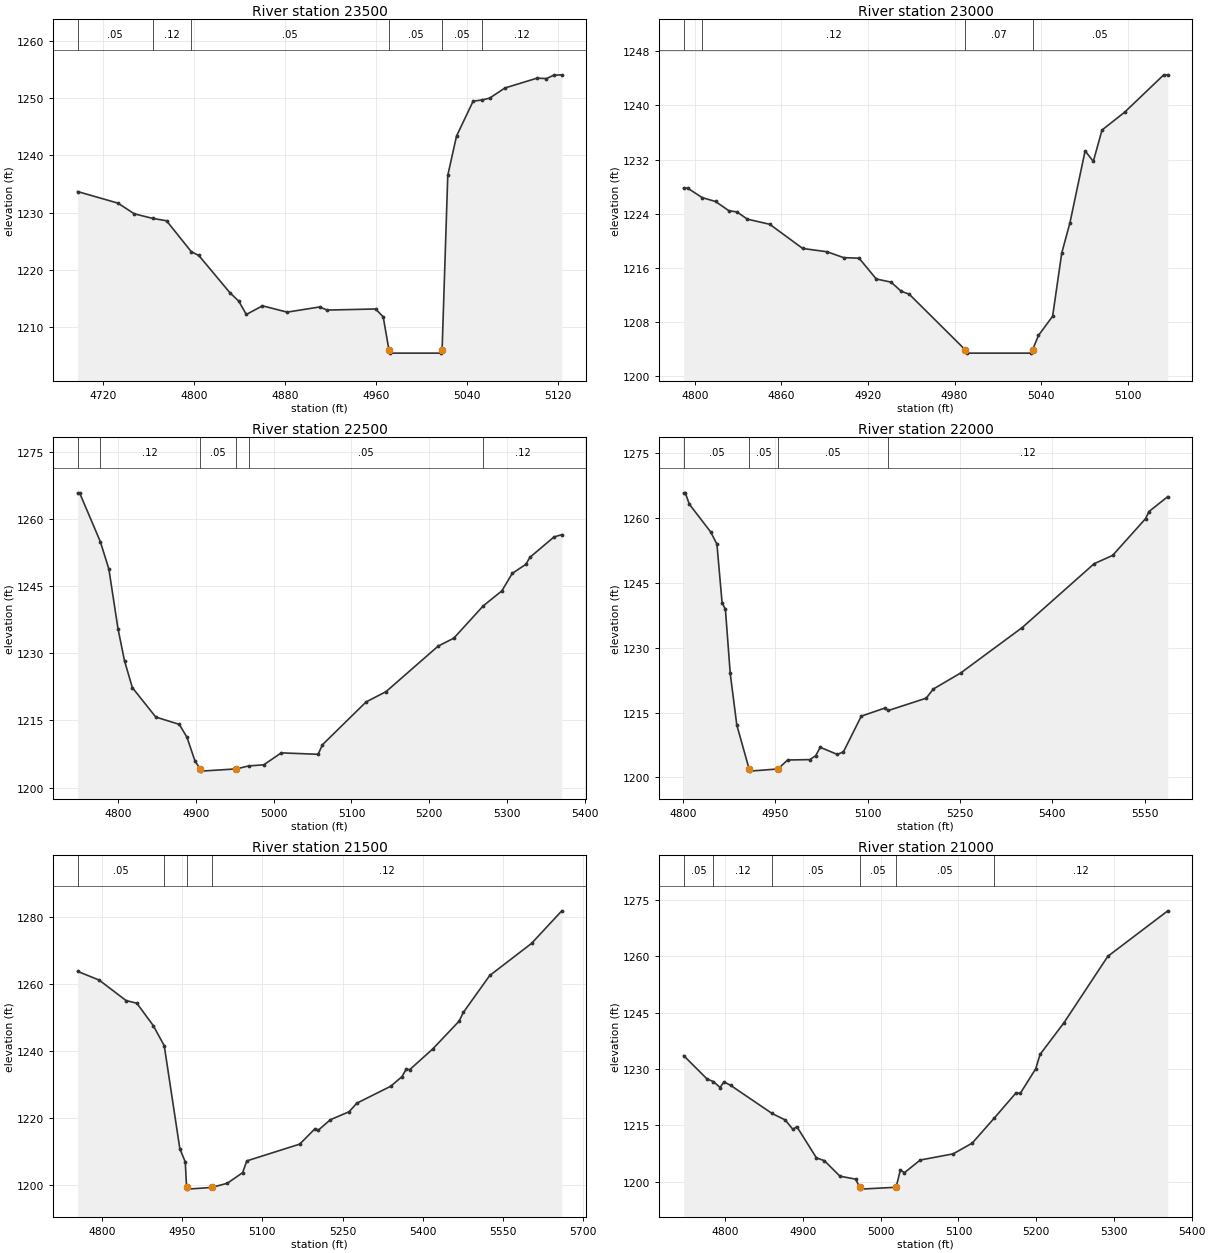
Type RM Length L Ch R = 1 ,23500   ,500,500,500
BEGIN DESCRIPTION:
FALL CREEK 47.0
END DESCRIPTION:
XS GIS Cut Line= 3
      2872505.67     10307753.13      2872707.24     10307527.58
      2872805.66     10307453.13
#Sta/Elev= 30
  4697.5 1233.66    4733 1231.64  4747.3 1229.78  4763.7 1228.97  4775.7 1228.57
  4797.5 1223.17  4804.1 1222.51  4831.7 1215.96  4839.2 1214.56  4845.9 1212.22
  4860.1 1213.73  4881.8 1212.63  4910.3 1213.53    4917 1212.99  4959.6 1213.18
  4966.3 1211.81  4971.4 1205.98  4972.4 1205.48  5017.1 1205.48  5018.1 1205.98
  5023.1 1236.49  5030.8 1243.34  5045.4 1249.42  5053.3 1249.64  5059.9 1249.95
  5073.3 1251.72  5101.6 1253.44  5109.9 1253.37  5116.2 1253.94  5123.4 1254.02
#Mann= 6 ,-1 , 0
  4697.5     .05       0  4763.7     .12       0  4797.5     .05       0
  4971.4     .05       0  5018.1     .05       0  5053.3     .12       0
Bank Sta=4971.4,5018.1
XS Rating Curve= 0 ,0
Exp/Cntr=0.3,0.1

Type RM Length L Ch R = 1 ,23000   ,500,500,500
BEGIN DESCRIPTION:
FALL CREEK 46.0
END DESCRIPTION:
XS GIS Cut Line= 3
       2872755.7     10308053.11      2872943.54     10307964.48
      2873055.65     10307903.13
#Sta/Elev= 30
  4792.3 1227.79    4795 1227.79  4805.2 1226.38  4814.4 1225.81  4823.7 1224.44
  4829.2 1224.27  4836.5  1223.2    4852 1222.44  4874.8 1218.87  4891.8 1218.38
  4903.1 1217.52  4913.9 1217.43  4925.8 1214.36    4936  1213.9  4943.1 1212.54
  4948.6 1212.12  4987.4 1203.91  4988.4 1203.41  5033.1 1203.41  5034.1 1203.91
  5038.2 1206.03    5048 1208.86  5054.3 1218.19    5060 1222.67  5070.5 1233.29
  5076.2 1231.73  5082.2 1236.36    5098 1239.02    5125 1244.52  5127.8 1244.52
#Mann= 4 ,-1 , 0
  4792.3     .05       0  4805.2     .12       0  4987.4     .07       0
  5034.1     .05       0
Bank Sta=4987.4,5034.1
XS Rating Curve= 0 ,0
Exp/Cntr=0.3,0.1

Type RM Length L Ch R = 1 ,22500   ,500,500,500
BEGIN DESCRIPTION:
FALL CREEK 45.0
END DESCRIPTION:
XS GIS Cut Line= 3
      2873155.69     10308653.09      2873181.67     10308402.24
      2873305.69     10308053.11
#Sta/Elev= 30
  4747.8 1265.86  4750.3 1265.86    4777 1254.96    4788 1248.81  4799.7 1235.52
  4808.1 1228.33  4818.2 1222.34  4848.3 1215.77  4878.5 1214.14  4888.4 1211.27
  4898.6 1206.02  4905.3 1204.19  4906.3 1203.69  4952.1 1204.19  4967.7 1204.85
  4987.2  1205.1  5009.7 1207.77  5057.1 1207.45  5062.7 1209.59  5118.8 1219.15
  5144.4 1221.44  5211.4 1231.61  5231.6 1233.39  5269.5 1240.61  5293.4 1243.96
  5306.8 1247.86  5324.2 1249.88  5329.5 1251.45  5360.4 1255.99  5370.5 1256.52
#Mann= 6 ,-1 , 0
  4747.8     .05       0    4777     .12       0  4905.3     .05       0
  4952.1     .12       0  4967.7     .05       0  5269.5     .12       0
Bank Sta=4905.3,4952.1
XS Rating Curve= 0 ,0
Exp/Cntr=0.3,0.1

Type RM Length L Ch R = 1 ,22000   ,500,500,500
BEGIN DESCRIPTION:
FALL CREEK 44.0
END DESCRIPTION:
XS GIS Cut Line= 3
      2873355.69     10308803.11      2873539.61     10308727.12
      2873805.69      10308203.1
#Sta/Elev= 30
    4801 1265.74  4803.7 1265.74  4810.2 1263.13    4845  1256.7  4855.1 1253.88
  4863.5 1240.35  4868.9 1238.83  4876.7 1224.06  4887.4 1212.12  4907.4 1201.97
  4908.4 1201.47  4954.2 1201.97    4970 1204.04  5006.2 1204.13  5015.7 1205.05
  5022.9 1206.97  5050.7 1205.33  5060.6 1205.91  5089.7 1214.17  5127.9 1216.03
  5133.8 1215.48  5195.2 1218.32  5206.6 1220.42  5251.2 1224.14  5351.2 1234.63
  5468.1 1249.38    5498 1251.28  5551.5 1259.77  5557.1 1261.42  5587.7 1264.87
#Mann= 4 ,-1 , 0
    4801     .05       0  4907.4     .05       0  4954.2     .05       0
  5133.8     .12       0
Bank Sta=4907.4,4954.2
XS Rating Curve= 0 ,0
Exp/Cntr=0.3,0.1

Type RM Length L Ch R = 1 ,21500   ,500,500,500
BEGIN DESCRIPTION:
FALL CREEK 43.0
END DESCRIPTION:
XS GIS Cut Line= 3
      2874005.69      10309053.1       2874032.6     10308809.18
      2874455.67     10308303.13
#Sta/Elev= 30
  4754.6 1263.73  4794.8 1261.14  4845.1 1255.05  4865.3 1254.24  4895.9  1247.6
  4916.5  1241.6  4945.7 1210.88  4955.8 1206.99  4958.3 1199.38  4959.3 1198.88
  5005.1 1199.38  5034.3 1200.62    5063 1203.78  5070.8 1207.29  5169.7 1212.28
  5198.3 1216.87  5204.8 1216.48  5226.9 1219.54  5262.1 1221.93  5276.4 1224.47
  5340.1 1229.54    5361 1232.41  5368.8 1234.63  5375.3 1234.46  5418.2  1240.6
  5467.7 1248.92  5475.5 1251.49  5524.9  1262.5    5603 1272.05  5659.6 1281.76
#Mann= 4 ,-1 , 0
  4754.6     .05       0  4916.5     .12       0  4958.3     .07       0
  5005.1     .12       0
Bank Sta=4958.3,5005.1
XS Rating Curve= 0 ,0
Exp/Cntr=0.3,0.1

Type RM Length L Ch R = 1 ,21000   ,500,500,500
BEGIN DESCRIPTION:
FALL CREEK 42.0
END DESCRIPTION:
XS GIS Cut Line= 3
      2874505.68     10309053.15      2874531.84       10308801.
      2874655.69     10308453.09
#Sta/Elev= 30
  4746.5 1233.57  4776.7 1227.33  4784.8 1226.65  4793.4 1225.07  4798.4 1226.57
  4806.9 1225.65  4860.3 1218.16  4877.2 1216.43  4887.1 1213.92  4892.1 1214.66
  4917.4 1206.33  4927.5 1205.61  4947.6 1201.47  4967.7 1200.69    4973 1198.53
    4974 1198.03  5019.8 1198.53  5025.3 1203.11  5030.6 1202.41  5050.8 1205.77
  5093.3 1207.42  5117.8 1210.29  5146.3 1216.99  5174.2 1223.67  5179.5  1223.5
  5199.4 1230.05    5205 1233.88  5235.8 1242.32  5292.2 1259.99  5369.3 1272.08
#Mann= 6 ,-1 , 0
  4746.5     .05       0  4784.8     .12       0  4860.3     .05       0
    4973     .05       0  5019.8     .05       0  5146.3     .12       0
Bank Sta=4973,5019.8
XS Rating Curve= 0 ,0
Exp/Cntr=0.3,0.1

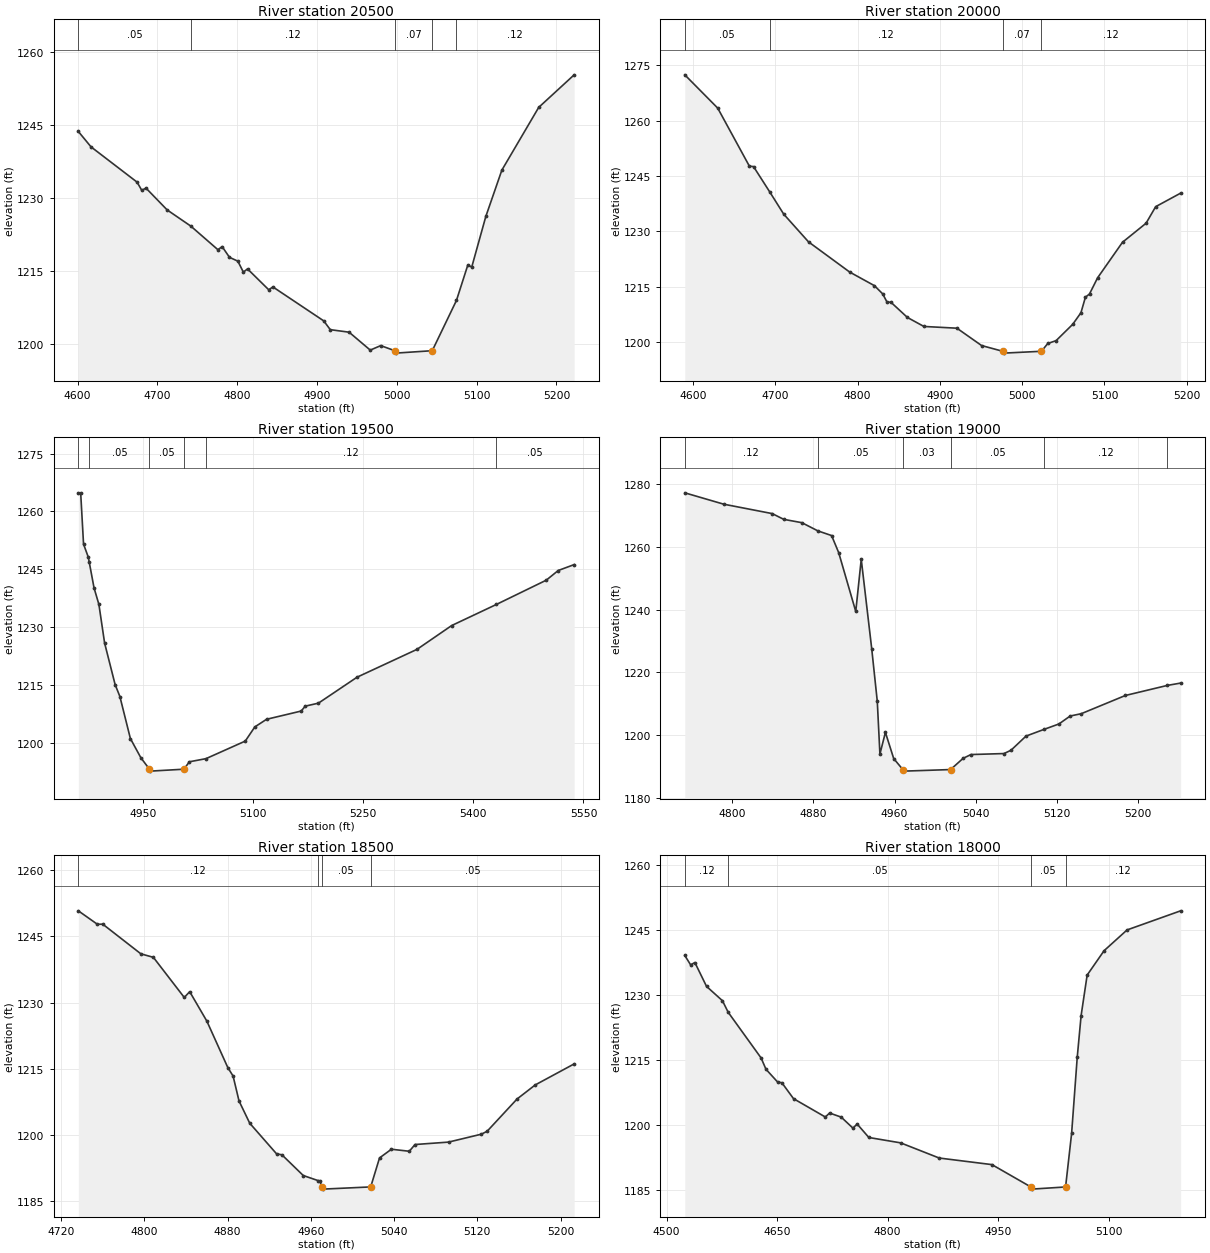
Type RM Length L Ch R = 1 ,20500   ,500,500,500
BEGIN DESCRIPTION:
FALL CREEK 41.0
END DESCRIPTION:
XS GIS Cut Line= 3
      2875155.67     10309203.07      2875031.18     10308823.88
      2875005.69     10308603.15
#Sta/Elev= 30
  4600.9 1243.73  4616.8 1240.56  4674.5  1233.3  4680.4 1231.61  4685.7 1232.07
  4712.2 1227.58  4741.9 1224.24  4775.8 1219.39  4781.1 1220.03  4790.3 1217.82
  4800.8 1217.03  4807.7 1214.77  4812.9 1215.44  4839.5 1211.14  4844.7 1211.73
  4908.4 1204.74  4916.6 1202.93  4940.2 1202.41  4966.7 1198.72  4979.8 1199.65
  4997.4  1198.6  4998.4  1198.1  5044.4  1198.6  5074.7 1208.94  5088.9 1216.21
  5093.9 1215.83  5111.5 1226.23  5131.6 1235.77  5177.8 1248.69  5222.2 1255.39
#Mann= 5 ,-1 , 0
  4600.9     .05       0  4741.9     .12       0  4997.4     .07       0
  5044.4     .12       0  5074.7     .12       0
Bank Sta=4997.4,5044.4
XS Rating Curve= 0 ,0
Exp/Cntr=0.3,0.1

Type RM Length L Ch R = 1 ,20000   ,500,500,500
BEGIN DESCRIPTION:
FALL CREEK 40.0
END DESCRIPTION:
XS GIS Cut Line= 3
      2875505.69     10309253.08       2875530.7     10308843.95
      2875505.68     10308653.08
#Sta/Elev= 30
  4590.1 1272.39  4630.1 1263.38  4668.6 1247.65  4673.6 1247.55  4693.3 1240.69
  4710.3 1234.67  4740.4 1227.17  4790.4    1219  4820.5 1215.31  4830.5  1213.1
  4835.7 1210.91  4840.7 1210.79  4860.6  1206.7  4880.6 1204.27  4920.7  1203.8
  4950.7  1199.1  4976.4 1197.55  4977.4 1197.05  5023.4 1197.55  5031.1 1199.66
  5041.2 1200.43  5061.4 1204.85  5071.4 1207.99  5076.8 1212.17  5081.8 1213.07
  5091.6 1217.43  5121.9 1227.07  5150.5 1232.21  5162.2  1236.7  5192.5 1240.36
#Mann= 4 ,-1 , 0
  4590.1     .05       0  4693.3     .12       0  4976.4     .07       0
  5023.4     .12       0
Bank Sta=4976.4,5023.4
XS Rating Curve= 0 ,0
Exp/Cntr=0.3,0.1

Type RM Length L Ch R = 1 ,19500   ,500,500,500
BEGIN DESCRIPTION:
FALL CREEK 39.0
END DESCRIPTION:
XS GIS Cut Line= 3
      2876105.66     10308803.09      2875999.69     10308714.54
      2875505.73     10308503.13
#Sta/Elev= 30
  4861.9 1264.82  4865.1 1264.82    4869 1251.52  4875.5 1248.12  4876.7  1246.9
  4883.3 1240.17  4889.9 1235.89  4897.7 1225.86    4912 1215.11  4918.5 1212.01
  4932.8 1201.11  4947.1 1196.12  4958.8 1193.16  4959.8 1192.66  5005.8 1193.16
  5013.1 1195.08  5035.7 1195.89  5089.3 1200.45  5102.3 1204.12  5118.3  1206.1
  5165.5 1208.24  5170.9  1209.5    5189 1210.29  5241.6 1217.02  5323.3 1224.24
  5370.4  1230.4  5431.4 1235.88  5499.3 1242.17  5515.6 1244.68  5537.3 1246.21
#Mann= 6 ,-1 , 0
  4861.9     .12       0  4876.7     .05       0  4958.8     .05       0
  5005.8     .05       0  5035.7     .12       0  5431.4     .05       0
Bank Sta=4958.8,5005.8
XS Rating Curve= 0 ,0
Exp/Cntr=0.3,0.1

Type RM Length L Ch R = 1 ,19000   ,500,500,500
BEGIN DESCRIPTION:
FALL CREEK 38.0
END DESCRIPTION:
XS GIS Cut Line= 3
      2876305.65      10308353.1      2876078.04     10308258.22
      2875855.64     10308353.13
#Sta/Elev= 30
  4753.4 1277.29  4791.8 1273.66  4839.5 1270.66  4850.9 1268.82  4868.7 1267.76
  4884.5 1265.14    4898 1263.65    4905 1258.19  4921.8 1239.42  4927.2 1256.08
  4937.5 1227.58    4943 1210.74  4945.6  1193.9    4951 1200.82  4959.2 1192.44
  4968.2 1188.95  4969.2 1188.45  5015.2 1188.95  5027.5 1192.52  5035.2 1193.74
  5067.8 1194.06  5074.7 1195.11  5089.5 1199.63  5107.6 1201.82  5121.9  1203.5
    5133 1206.04  5143.9 1206.78  5187.4  1212.6  5228.7 1215.81  5241.8 1216.56
#Mann= 6 ,-1 , 0
  4753.4     .12       0  4884.5     .05       0  4968.2     .03       0
  5015.2     .05       0  5107.6     .12       0  5228.7     .05       0
Bank Sta=4968.2,5015.2
XS Rating Curve= 0 ,0
Exp/Cntr=0.3,0.1

Type RM Length L Ch R = 1 ,18500   ,500,500,500
BEGIN DESCRIPTION:
FALL CREEK 37.0
END DESCRIPTION:
XS GIS Cut Line= 3
       2876105.7     10307753.11      2875849.76     10307815.33
      2875655.69     10307903.11
#Sta/Elev= 30
  4736.6 1250.81  4754.9 1247.76  4760.1 1247.78  4796.7 1241.05  4808.7 1240.26
  4838.4 1231.15  4843.6 1232.47  4860.1 1225.78  4880.2 1215.26  4885.3 1213.32
    4891 1207.67  4901.3 1202.62  4927.1 1195.67  4932.2 1195.46  4952.7 1190.76
    4967  1189.6  4968.8 1189.51  4970.4 1188.17  4971.4 1187.67  5017.5 1188.17
    5026 1194.75  5037.4 1196.72  5054.6 1196.26  5060.1 1197.79  5092.3 1198.34
  5123.9 1200.14  5129.4  1200.8  5158.1 1208.11  5175.6 1211.31    5213 1216.08
#Mann= 4 ,-1 , 0
  4736.6     .12       0    4967     .05       0  4970.4     .05       0
  5017.5     .05       0
Bank Sta=4970.4,5017.5
XS Rating Curve= 0 ,0
Exp/Cntr=0.3,0.1

Type RM Length L Ch R = 1 ,18000   ,500,500,500
BEGIN DESCRIPTION:
FALL CREEK 36.0
END DESCRIPTION:
XS GIS Cut Line= 3
      2876055.68     10307603.11      2875642.82     10307367.61
      2875455.72     10307303.12
#Sta/Elev= 30
  4524.7 1239.09  4532.6 1236.93  4538.4 1237.46  4554.2 1231.96  4575.8 1228.65
  4583.6 1225.98  4628.3 1215.43  4634.9 1212.83  4650.7 1209.88  4656.5 1209.71
  4672.3 1206.04  4715.5  1201.8  4721.3 1202.72  4737.1 1201.77    4753 1199.23
  4758.7 1200.18  4774.6 1197.07  4817.8 1195.83  4870.1 1192.33  4941.7 1190.81
  4994.6 1185.65  4995.6 1185.15  5041.7 1185.65  5049.9 1198.02  5057.5 1215.54
  5062.8 1225.23    5071 1234.57    5094  1240.2  5125.2 1244.99  5197.9  1249.4
#Mann= 4 ,-1 , 0
  4524.7     .12       0  4583.6     .05       0  4994.6     .05       0
  5041.7     .12       0
Bank Sta=4994.6,5041.7
XS Rating Curve= 0 ,0
Exp/Cntr=0.3,0.1

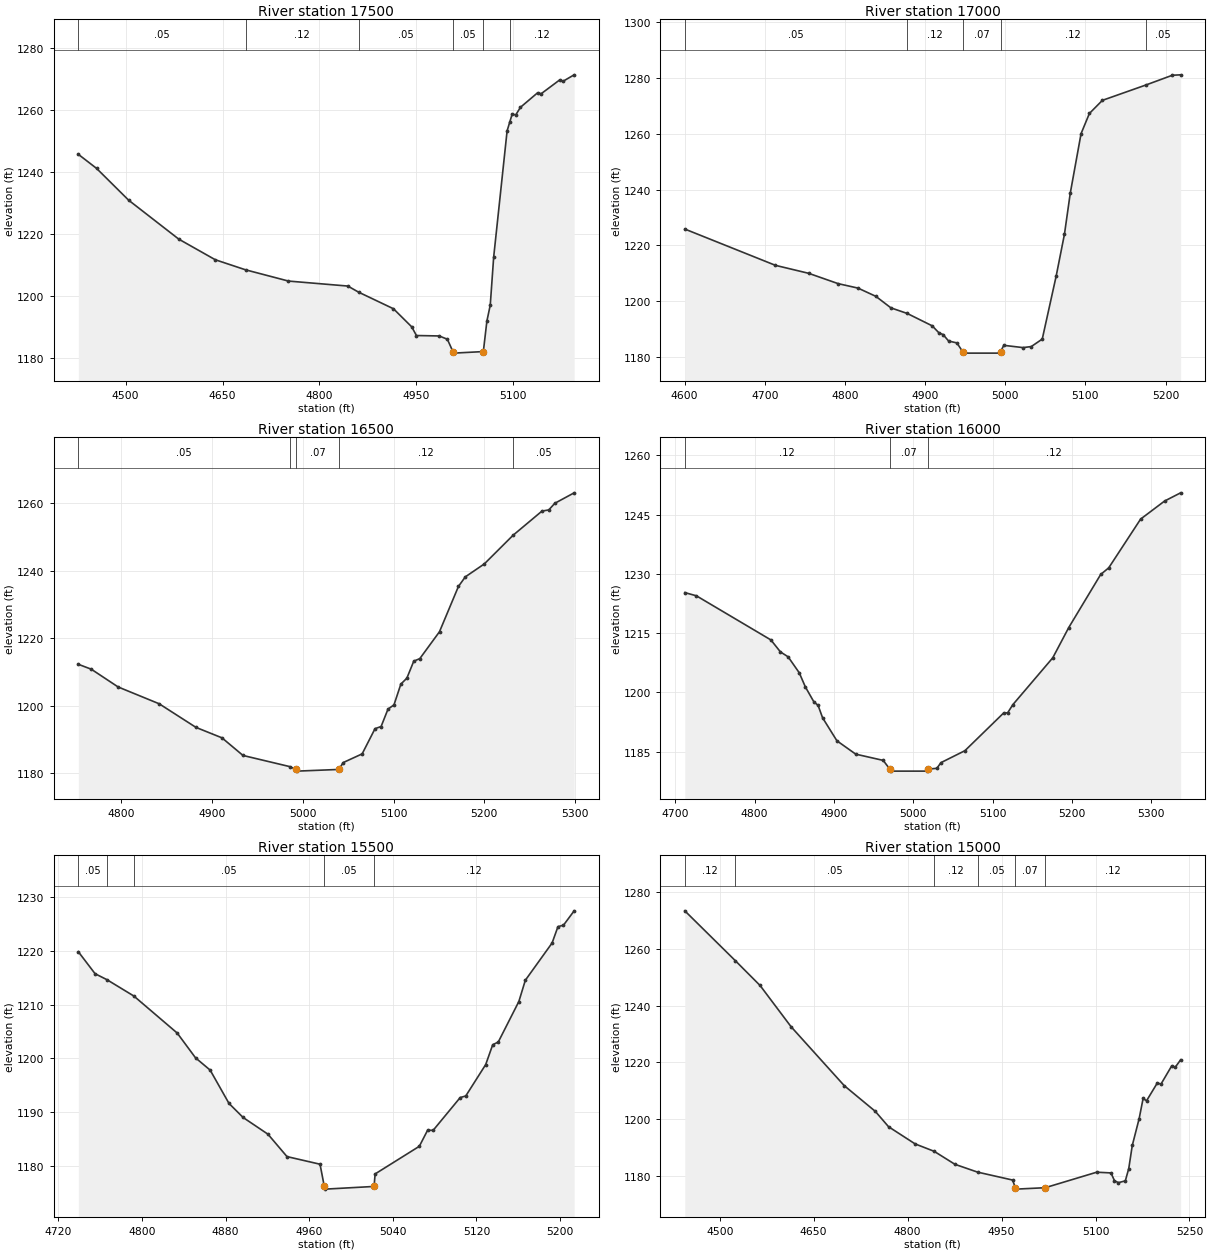
Type RM Length L Ch R = 1 ,17500   ,500,500,500
BEGIN DESCRIPTION:
FALL CREEK 35.0
END DESCRIPTION:
XS GIS Cut Line= 3
       2876255.7     10307353.13      2875857.95     10306940.26
      2875805.69     10306753.12
#Sta/Elev= 30
  4426.7  1245.7  4454.9 1241.17  4504.6  1230.9  4582.2 1218.34  4638.8 1211.68
  4685.6 1208.44    4752 1204.81  4843.9  1203.2  4860.6 1201.23  4914.6 1195.87
  4942.9 1190.02  4950.1 1187.24  4985.4  1187.1    4998 1186.04  5006.6 1182.06
  5007.6 1181.56  5053.7 1182.06  5059.2  1191.9  5064.4 1197.04  5069.7 1212.54
  5090.5 1253.28  5094.6  1256.1  5098.5 1258.79  5103.7 1258.37  5111.2 1260.88
  5137.9 1265.59  5143.1 1265.23    5172 1269.72  5177.2 1269.29  5194.3 1271.35
#Mann= 6 ,-1 , 0
  4426.7     .05       0  4685.6     .12       0  4860.6     .05       0
  5006.6     .05       0  5053.7     .05       0  5094.6     .12       0
Bank Sta=5006.6,5053.7
XS Rating Curve= 0 ,0
Exp/Cntr=0.3,0.1

Type RM Length L Ch R = 1 ,17000   ,500,500,500
BEGIN DESCRIPTION:
FALL CREEK 34.0
END DESCRIPTION:
XS GIS Cut Line= 3
      2876405.68     10307153.11      2876312.12     10306764.52
      2876255.69     10306553.12
#Sta/Elev= 30
  4600.3 1225.89  4713.4 1212.89  4754.8 1210.04  4791.6 1206.34  4816.3 1204.75
  4838.6  1201.8  4857.4 1197.67  4877.8 1195.66  4908.9 1191.24  4917.3 1188.73
  4922.5 1188.11  4929.4 1185.79  4939.7 1185.12    4947 1181.96    4948 1181.46
  4993.2 1181.46  4994.2 1181.96  4998.2 1184.25  5022.2 1183.44  5032.5 1183.81
  5046.2 1186.49  5063.6 1209.11  5073.9 1224.06  5081.1 1238.66  5094.6 1260.04
    5105 1267.28  5121.2 1271.97  5175.4 1277.46  5208.5 1280.96  5218.8 1281.11
#Mann= 5 ,-1 , 0
  4600.3     .05       0  4877.8     .12       0    4947     .07       0
  4994.2     .12       0  5175.4     .05       0
Bank Sta=4947,4994.2
XS Rating Curve= 0 ,0
Exp/Cntr=0.3,0.1

Type RM Length L Ch R = 1 ,16500   ,500,500,500
BEGIN DESCRIPTION:
FALL CREEK 33.0
END DESCRIPTION:
XS GIS Cut Line= 3
      2876905.67     10306903.07       2876803.7     10306677.44
       2876605.7     10306453.13
#Sta/Elev= 30
  4752.4 1212.27  4766.7 1210.81  4796.3 1205.54  4841.5 1200.56  4882.2 1193.54
  4910.8 1190.45    4934 1185.22  4985.3 1181.93  4992.5 1181.07  4993.5 1180.57
  5039.7 1181.07  5044.5 1183.11  5065.4 1185.69  5079.6 1193.17  5086.3 1193.81
  5093.9 1198.97  5100.5 1200.23  5108.1  1206.4  5114.7 1208.15  5122.3 1213.19
    5129 1213.96  5150.7 1221.94  5171.6 1235.38  5179.2 1238.22  5200.1 1242.05
  5231.8 1250.55  5263.7 1257.73  5271.2 1258.08  5277.9 1260.05  5299.2 1263.15
#Mann= 5 ,-1 , 0
  4752.4     .05       0  4985.3     .12       0  4992.5     .07       0
  5039.7     .12       0  5231.8     .05       0
Bank Sta=4992.5,5039.7
XS Rating Curve= 0 ,0
Exp/Cntr=0.3,0.1

Type RM Length L Ch R = 1 ,16000   ,500,500,500
BEGIN DESCRIPTION:
FALL CREEK 32.0
END DESCRIPTION:
XS GIS Cut Line= 3
       2877405.7     10306853.15      2877294.05     10306587.68
      2877255.68     10306253.07
#Sta/Elev= 30
    4712 1225.25  4726.6 1224.44  4820.5 1213.26  4832.5 1210.23  4842.2 1208.98
  4856.2 1204.95  4863.9 1201.37  4874.5 1197.63    4880 1196.66  4885.6 1193.55
  4903.7 1187.71  4927.4 1184.33    4962 1182.75  4970.4 1180.53  4971.4 1180.03
  5016.9 1180.03  5017.9 1180.53  5029.6 1180.74  5034.8 1182.18    5065 1185.21
  5113.8 1194.76  5118.8 1194.79  5125.4 1196.87  5175.7 1208.74  5195.8 1216.39
  5236.1 1229.85  5246.2 1231.52  5286.4 1243.87  5316.6 1248.44  5336.8 1250.52
#Mann= 3 ,-1 , 0
    4712     .12       0  4970.4     .07       0  5017.9     .12       0
Bank Sta=4970.4,5017.9
XS Rating Curve= 0 ,0
Exp/Cntr=0.3,0.1

Type RM Length L Ch R = 1 ,15500   ,500,500,500
BEGIN DESCRIPTION:
FALL CREEK 31.0
END DESCRIPTION:
XS GIS Cut Line= 3
      2877855.68     10306703.09      2877775.53     10306454.91
       2877705.7     10306253.15
#Sta/Elev= 30
  4739.2 1219.86  4755.2 1215.77  4766.6 1214.65  4792.3 1211.61  4833.8 1204.71
  4851.3  1200.1  4865.3 1197.81  4883.3 1191.61  4896.8 1188.99  4920.6 1185.87
  4938.8  1181.7  4970.4 1180.28  4974.5 1176.14  4975.5 1175.64  5022.1 1176.14
  5023.1 1178.47  5065.4 1183.62  5073.3 1186.61  5078.6 1186.59  5104.5  1192.7
  5109.8 1192.99  5128.9 1198.85  5135.6 1202.54  5140.9 1203.04  5160.6 1210.59
  5166.8 1214.55  5192.4 1221.49    5198 1224.53  5203.3 1224.81  5213.5 1227.48
#Mann= 5 ,-1 , 0
  4739.2     .05       0  4766.6     .12       0  4792.3     .05       0
  4974.5     .05       0  5022.1     .12       0
Bank Sta=4974.5,5022.1
XS Rating Curve= 0 ,0
Exp/Cntr=0.3,0.1

Type RM Length L Ch R = 1 ,15000   ,500,500,500
BEGIN DESCRIPTION:
FALL CREEK 30.0
END DESCRIPTION:
XS GIS Cut Line= 3
      2878655.67      10306703.1      2878256.03     10306316.97
      2878355.67     10306103.15
#Sta/Elev= 30
  4444.3 1273.36  4524.7 1255.86  4564.5 1247.06  4613.9 1232.56  4698.8  1211.8
  4748.5 1202.72  4769.6 1197.32    4812 1191.27  4842.4 1188.66  4875.6 1184.08
  4911.7 1181.33  4967.6 1178.54  4972.1 1175.84  4973.1 1175.34  5019.7 1175.84
  5101.9  1181.3  5124.7 1181.05  5130.3 1178.31  5136.6 1177.62  5147.6 1178.25
  5153.1  1182.6  5158.7 1190.71  5169.7 1200.18    5176 1207.26  5181.5 1206.46
  5198.9 1212.81  5204.4 1212.28  5221.7 1218.76  5227.3 1218.27  5235.9 1220.89
#Mann= 6 ,-1 , 0
  4444.3     .12       0  4524.7     .05       0  4842.4     .12       0
  4911.7     .05       0  4972.1     .07       0  5019.7     .12       0
Bank Sta=4972.1,5019.7
XS Rating Curve= 0 ,0
Exp/Cntr=0.3,0.1

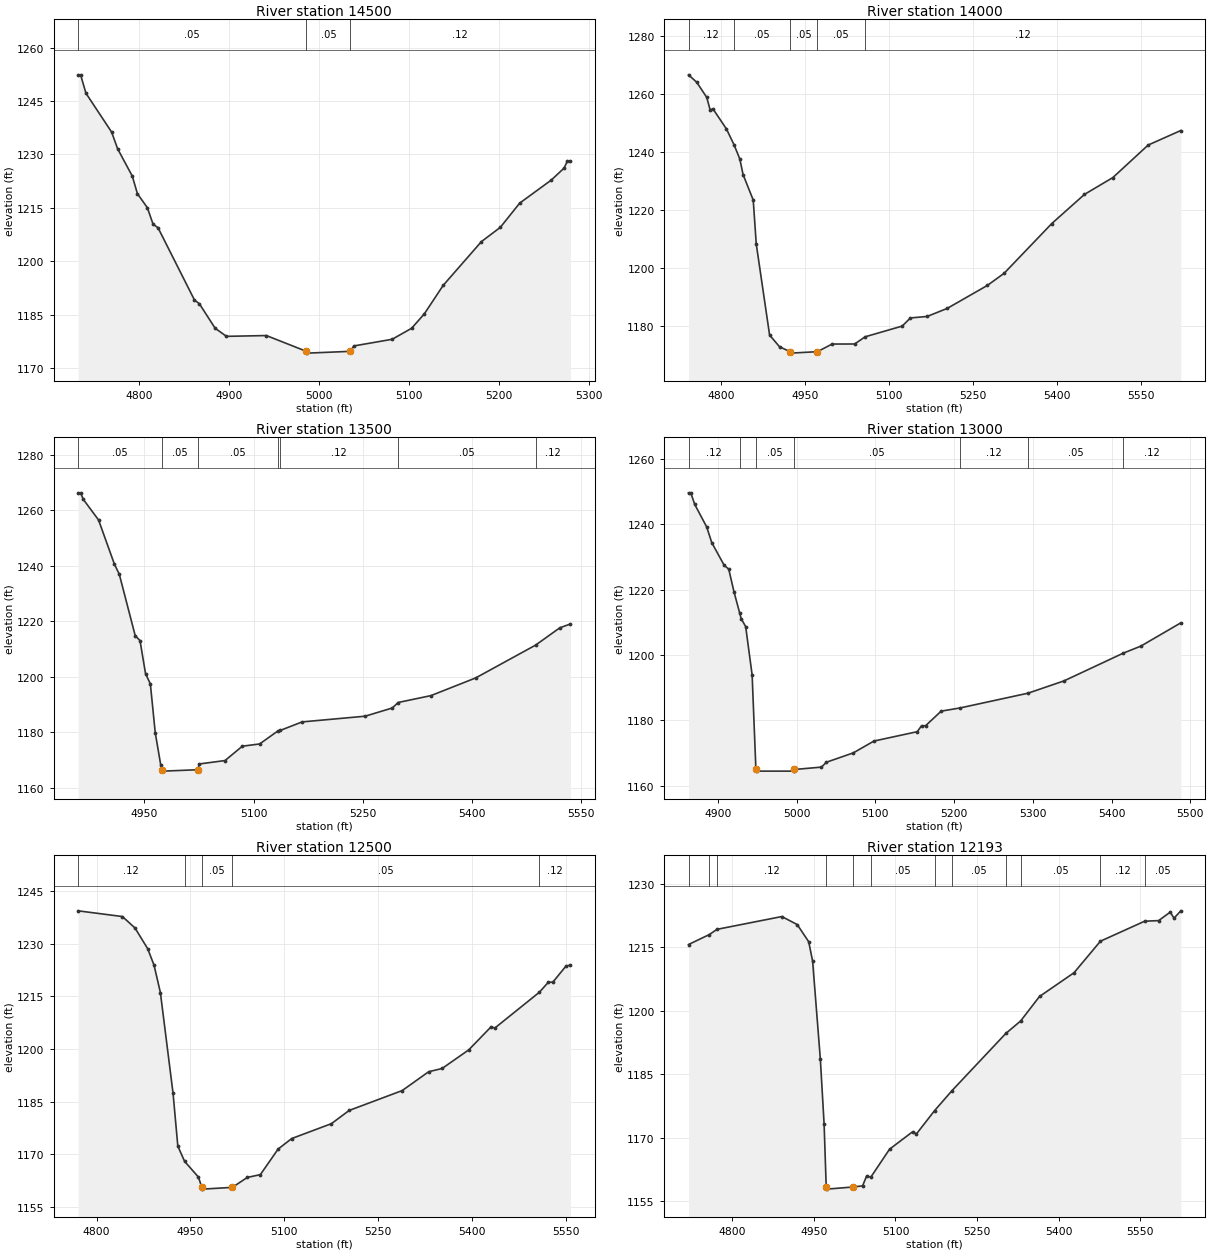
Type RM Length L Ch R = 1 ,14500   ,500,500,500
BEGIN DESCRIPTION:
FALL CREEK 29.0
END DESCRIPTION:
XS GIS Cut Line= 3
      2878855.67     10306453.08      2878744.13     10306209.28
       2878555.7     10306003.12
#Sta/Elev= 30
  4731.9 1252.35  4734.6 1252.35  4740.6 1247.17  4769.1 1236.29  4775.8 1231.59
  4792.1 1223.93  4797.8 1218.99  4808.8 1215.09  4815.2 1210.44  4820.7 1209.44
  4861.2 1189.18  4866.7 1188.11  4884.2 1181.25  4896.8 1178.97  4941.2 1179.19
  4985.7 1174.76  4986.7 1174.26  5034.5 1174.76  5038.5 1176.28    5081 1178.14
  5102.6 1181.22  5116.7 1185.23  5137.8 1193.28  5180.3 1205.55  5201.3 1209.55
  5222.9 1216.36    5258 1222.82  5272.2 1226.17  5275.9 1228.16  5279.3 1228.16
#Mann= 3 ,-1 , 0
  4731.9     .05       0  4985.7     .05       0  5034.5     .12       0
Bank Sta=4985.7,5034.5
XS Rating Curve= 0 ,0
Exp/Cntr=0.3,0.1

Type RM Length L Ch R = 1 ,14000   ,500,500,500
BEGIN DESCRIPTION:
FALL CREEK 28.0
END DESCRIPTION:
XS GIS Cut Line= 3
      2879455.66      10306153.1      2879217.41     10306054.11
      2878705.71     10305703.13
#Sta/Elev= 30
    4742 1266.69  4756.6 1264.15  4774.5 1258.93  4780.5 1254.68  4785.9 1254.88
  4809.7 1248.03  4823.3 1242.57  4833.6 1237.66  4839.4  1232.3  4857.5 1223.52
  4862.9 1208.37  4886.7 1176.99  4904.4 1172.95  4923.3 1171.25  4924.3 1170.75
  4972.1 1171.25  4998.2 1173.88  5038.5  1173.9  5057.2 1176.38  5123.4 1180.08
    5138 1182.88  5167.8 1183.39  5203.6 1186.16  5275.4  1194.1  5305.2 1198.27
  5390.1 1215.39  5448.6 1225.47  5499.3 1231.28  5562.3 1242.49  5620.5 1247.49
#Mann= 5 ,-1 , 0
    4742     .12       0  4823.3     .05       0  4923.3     .05       0
  4972.1     .05       0  5057.2     .12       0
Bank Sta=4923.3,4972.1
XS Rating Curve= 0 ,0
Exp/Cntr=0.3,0.1

Type RM Length L Ch R = 1 ,13500   ,500,500,500
BEGIN DESCRIPTION:
FALL CREEK 27.0
END DESCRIPTION:
XS GIS Cut Line= 3
      2879655.68      10305803.1      2879549.19     10305710.68
      2879055.67      10305503.1
#Sta/Elev= 30
    4859 1266.27  4862.3 1266.27  4866.1  1263.9    4887 1256.51  4908.9 1240.52
  4915.5 1236.97  4937.4 1214.83    4944 1213.06  4951.6 1201.13  4958.2 1197.48
  4964.9 1179.92  4972.5 1168.23  4974.6 1166.56  4975.6 1166.06  5023.4 1166.56
  5025.5 1168.64  5060.8 1169.87  5084.6 1175.04  5108.3 1175.84  5133.3  1180.5
  5136.8 1180.73  5166.7 1183.78  5253.3 1185.84  5290.8 1188.81  5298.6 1190.77
  5343.7 1193.25  5405.2 1199.62  5487.6 1211.45  5520.8 1217.67  5535.4 1219.05
#Mann= 7 ,-1 , 0
    4859     .05       0  4974.6     .05       0  5023.4     .05       0
  5133.3     .05       0  5136.8     .12       0  5298.6     .05       0
  5487.6     .12       0
Bank Sta=4974.6,5023.4
XS Rating Curve= 0 ,0
Exp/Cntr=0.3,0.1

Type RM Length L Ch R = 1 ,13000   ,500,500,500
BEGIN DESCRIPTION:
FALL CREEK 26.0
END DESCRIPTION:
XS GIS Cut Line= 3
      2879755.72     10305153.09       2879636.8     10305221.53
      2879155.67     10305303.11
#Sta/Elev= 30
  4862.8 1249.65  4865.7 1249.65  4870.7 1246.11  4885.9  1239.2  4892.3 1234.42
  4908.1 1227.46  4913.9 1226.28  4920.5 1219.39  4927.7 1212.92  4929.7 1211.12
  4935.4 1208.67  4943.6  1193.9  4948.4 1164.92  4949.4 1164.42  4996.2 1164.42
  4997.2 1164.92  5031.6 1165.65    5038 1167.15  5072.1 1170.01  5098.3 1173.63
  5153.3  1176.5  5158.7  1178.3  5163.8 1178.31  5183.7 1182.79  5207.9 1183.78
    5294 1188.29  5339.7 1192.06  5415.2 1200.58  5437.3 1202.71    5488 1209.83
#Mann= 7 ,-1 , 0
  4862.8     .12       0  4927.7     .05       0  4948.4     .05       0
  4997.2     .05       0  5207.9     .12       0    5294     .05       0
  5415.2     .12       0
Bank Sta=4948.4,4997.2
XS Rating Curve= 0 ,0
Exp/Cntr=0.3,0.1

Type RM Length L Ch R = 1 ,12500   ,307,307,307
BEGIN DESCRIPTION:
FALL CREEK 25.0
END DESCRIPTION:
XS GIS Cut Line= 3
      2879655.64     10304753.12      2879428.98     10304788.51
      2879055.68     10305203.12
#Sta/Elev= 30
  4770.6 1239.38  4841.4 1237.75  4861.6 1234.48  4881.9 1228.56    4892 1223.88
  4902.1 1216.12  4922.4 1187.37    4930 1172.38  4940.8 1168.06  4962.9 1163.58
  4968.4 1160.64  4969.4 1160.14  5017.2 1160.64  5041.1 1163.47    5062 1164.27
  5090.4 1171.55  5112.1 1174.54  5175.6 1178.78    5204 1182.54  5288.8  1188.2
  5331.1 1193.56  5352.7  1194.5  5395.3  1199.8  5430.5 1206.27  5437.2 1206.04
  5508.2  1216.2  5522.4 1219.02  5529.9  1219.1  5550.8 1223.66  5557.9 1223.92
#Mann= 5 ,-1 , 0
  4770.6     .12       0  4940.8     .05       0  4968.4     .05       0
  5017.2     .05       0  5508.2     .12       0
Bank Sta=4968.4,5017.2
XS Rating Curve= 0 ,0
Exp/Cntr=0.3,0.1

Type RM Length L Ch R = 1 ,12193   ,693,693,693
BEGIN DESCRIPTION:
Mapping XS 5fa3b652
END DESCRIPTION:
XS GIS Cut Line= 2
       2879370.1     10304414.72      2878740.76     10305065.76
#Sta/Elev= 30
  4719.3 1215.63  4757.4 1217.97  4771.8 1219.22    4891 1222.24  4919.3 1220.34
  4940.4 1216.29  4947.6 1211.69  4961.8 1188.57  4968.7 1173.29  4972.6 1158.37
  4973.6 1157.87  5021.5 1158.37  5039.5 1158.64  5046.7 1160.91  5054.9 1160.75
  5089.1  1167.3  5131.5 1171.42  5138.5  1170.9  5171.8 1176.39  5203.6 1181.08
    5303 1194.64  5330.2 1197.58  5364.9 1203.36  5428.4 1208.97    5477 1216.42
  5558.3 1221.14    5584 1221.28  5605.4 1223.29  5612.3 1221.84  5624.8 1223.59
#Mann= 12 ,-1 , 0
  4719.3     .12       0  4757.4     .05       0  4771.8     .12       0
  4972.6     .07       0  5021.5     .12       0  5054.9     .05       0
  5171.8     .12       0  5203.6     .05       0    5303     .12       0
  5330.2     .05       0    5477     .12       0  5558.3     .05       0
Bank Sta=4972.6,5021.5
XS Rating Curve= 0 ,0
Exp/Cntr=0.3,0.1

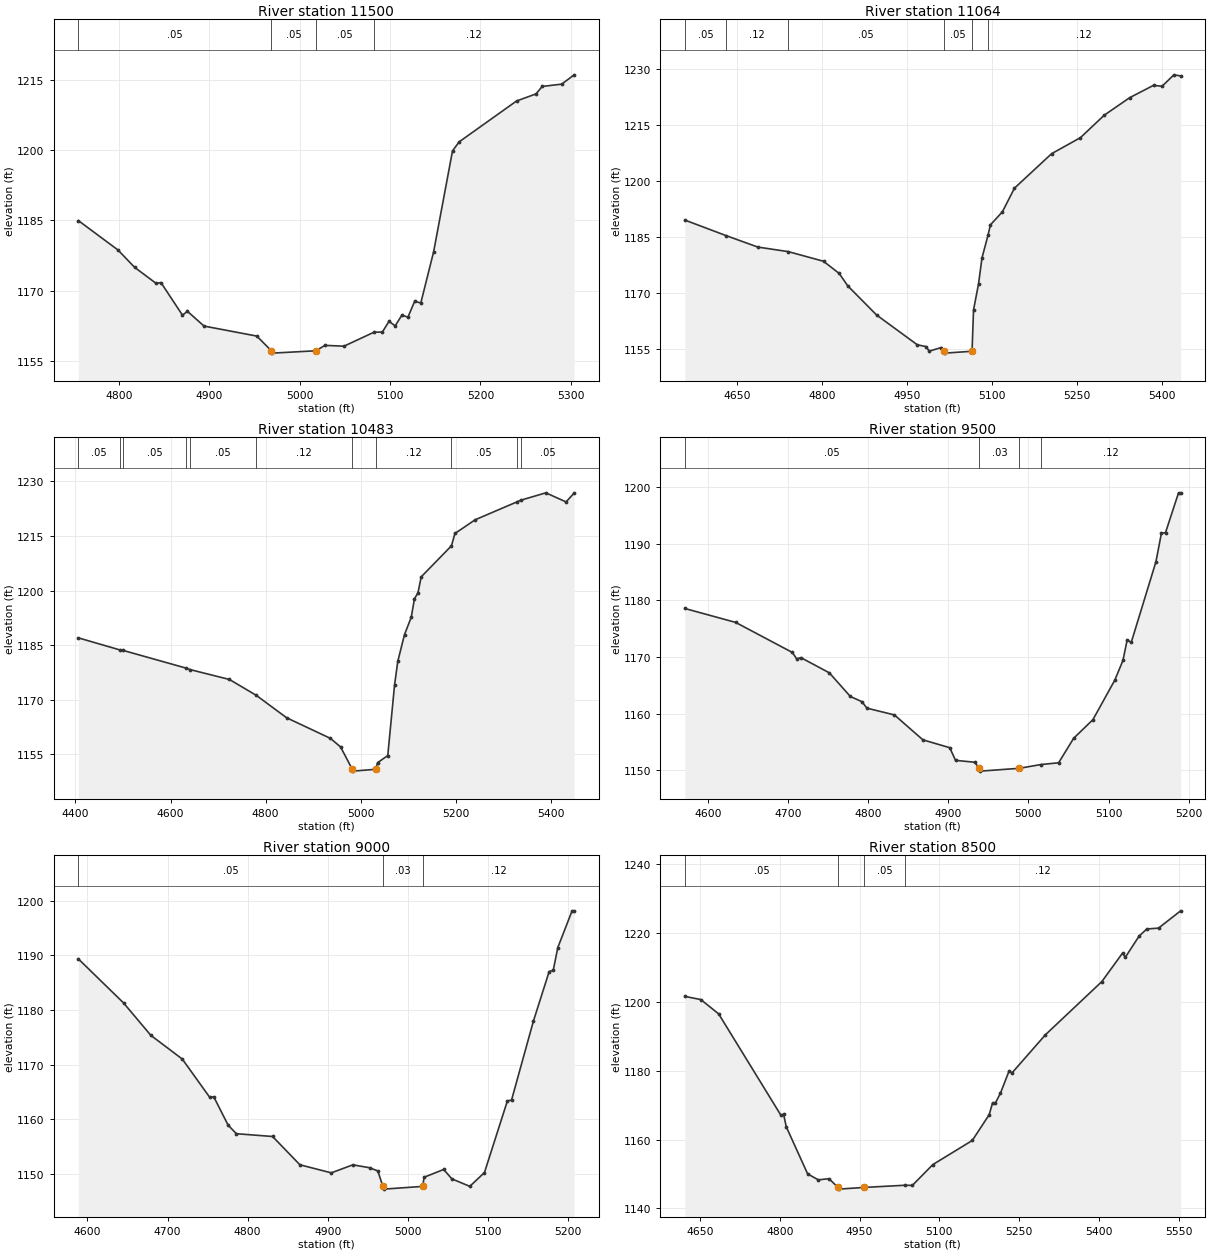
Type RM Length L Ch R = 1 ,11500   ,436,436,436
BEGIN DESCRIPTION:
FALL CREEK 23.0
END DESCRIPTION:
XS GIS Cut Line= 3
      2878955.69     10304203.11      2878729.38     10304108.73
      2878505.71     10303903.14
#Sta/Elev= 30
  4754.8 1184.97  4798.7 1178.69  4817.1 1174.99  4840.9 1171.56  4846.3 1171.73
  4870.1 1164.77  4875.6 1165.59    4894 1162.44  4952.4  1160.3  4968.6 1157.16
  4969.6 1156.66  5017.8 1157.16  5027.9 1158.32  5048.9 1158.14  5082.3 1161.14
  5091.4 1161.15  5098.8 1163.45  5105.6 1162.48    5113 1164.75  5119.8 1164.36
  5127.2 1167.73    5134 1167.37  5148.2  1178.3  5169.1 1199.85  5176.5 1201.79
    5240 1210.51  5261.6 1212.03  5268.4 1213.62    5290 1214.11  5303.8  1216.1
#Mann= 4 ,-1 , 0
  4754.8     .05       0  4968.6     .05       0  5017.8     .05       0
  5082.3     .12       0
Bank Sta=4968.6,5017.8
XS Rating Curve= 0 ,0
Exp/Cntr=0.3,0.1

Type RM Length L Ch R = 1 ,11064   ,581,581,581
BEGIN DESCRIPTION:
Mapping XS 2515aba7
END DESCRIPTION:
XS GIS Cut Line= 2
      2879229.08     10303958.96      2878502.04     10303470.66
#Sta/Elev= 30
    4557 1189.52  4629.9 1185.36  4685.8  1182.3  4739.9 1181.07    4802  1178.5
  4829.8 1175.23  4844.8 1171.93  4895.8 1164.13  4967.8 1156.16  4982.7 1155.71
  4988.9 1154.47  5009.9 1155.43  5015.2 1154.44  5016.2 1153.94  5064.4 1154.44
    5067 1165.48  5075.9 1172.49  5081.9 1179.36  5092.6 1185.47  5096.9 1188.24
  5117.9  1191.7  5139.3 1198.04  5204.9 1207.26  5255.9 1211.55  5297.9 1217.55
  5342.9 1222.24  5384.9 1225.53  5399.9 1225.27  5420.9 1228.34  5432.8 1228.05
#Mann= 6 ,-1 , 0
    4557     .05       0  4629.9     .12       0  4739.9     .05       0
  5015.2     .05       0  5064.4     .05       0  5092.6     .12       0
Bank Sta=5015.2,5064.4
XS Rating Curve= 0 ,0
Exp/Cntr=0.3,0.1

Type RM Length L Ch R = 1 ,10483   ,983,983,983
BEGIN DESCRIPTION:
Mapping XS a23b5feb
END DESCRIPTION:
XS GIS Cut Line= 2
      2879543.72     10303644.27      2878839.57     10302875.12
#Sta/Elev= 30
  4406.1    1187  4493.6 1183.68  4500.9 1183.53  4632.2 1178.71  4640.7  1178.3
  4723.9 1175.57  4780.4 1171.21  4844.2 1165.05  4936.4 1159.39  4957.7 1157.03
  4982.3  1150.9  4983.3  1150.4  5031.6  1150.9  5035.3  1152.7  5056.9 1154.68
  5071.1 1173.95  5077.9 1180.51  5092.1  1187.9  5106.3 1192.67    5113 1197.74
  5120.4 1199.35  5127.2 1203.75  5190.9 1212.29  5198.1 1215.66  5240.7 1219.43
  5328.2 1224.32  5336.2 1224.78  5389.3 1226.83  5431.9 1224.33  5448.9 1226.78
#Mann= 11 ,-1 , 0
  4406.1     .05       0  4493.6     .12       0  4500.9     .05       0
  4632.2     .12       0  4640.7     .05       0  4780.4     .12       0
  4982.3     .07       0  5031.6     .12       0  5190.9     .05       0
  5328.2     .12       0  5336.2     .05       0
Bank Sta=4982.3,5031.6
XS Rating Curve= 0 ,0
Exp/Cntr=0.3,0.1

Type RM Length L Ch R = 1 ,9500    ,500,500,500
BEGIN DESCRIPTION:
FALL CREEK 19.0
END DESCRIPTION:
XS GIS Cut Line= 3
      2880055.68     10303153.08      2879948.44     10302738.11
      2879905.68     10302553.09
#Sta/Elev= 30
  4571.4 1178.56  4634.9  1176.1  4705.6  1170.8    4711 1169.66  4716.2 1169.89
  4751.7 1167.21  4777.9 1163.04  4792.3 1162.12  4798.6 1160.98  4832.9 1159.78
  4868.4 1155.39  4901.9    1154  4909.1 1151.77  4932.9 1151.44    4939 1150.37
    4940 1149.87  4988.8 1150.37  5015.5 1151.03  5037.7 1151.34  5056.5 1155.67
  5080.5 1158.95  5107.8 1165.92    5118 1169.41  5123.2 1173.02  5128.3 1172.57
  5159.1  1186.8  5165.9  1191.8  5171.1 1191.96  5187.3 1198.96  5189.9 1198.96
#Mann= 4 ,-1 , 0
  4571.4     .05       0    4939     .03       0  4988.8     .05       0
  5015.5     .12       0
Bank Sta=4939,4988.8
XS Rating Curve= 0 ,0
Exp/Cntr=0.3,0.1

Type RM Length L Ch R = 1 ,9000    ,500,500,500
BEGIN DESCRIPTION:
FALL CREEK 18.0
END DESCRIPTION:
XS GIS Cut Line= 3
      2880555.69     10303153.13      2880444.64       10302757.
      2880405.68     10302553.09
#Sta/Elev= 30
  4588.6 1189.37    4645 1181.31  4679.1 1175.37  4718.4 1171.02  4752.5 1164.04
  4757.7  1164.1  4775.6 1158.92  4785.9 1157.35  4831.1 1156.84  4865.2 1151.66
  4904.4 1150.18  4931.3 1151.65  4952.1 1151.12  4962.5 1150.53  4968.8  1147.7
  4969.8  1147.2  5018.6  1147.7  5020.2 1149.37  5044.7  1150.8  5054.9 1149.08
  5077.3 1147.71  5095.6 1150.23  5124.3 1163.38  5129.4 1163.49  5156.7 1177.96
  5176.4 1187.05  5181.5 1187.29  5187.2 1191.45    5205 1198.17  5207.6 1198.17
#Mann= 3 ,-1 , 0
  4588.6     .05       0  4968.8     .03       0  5018.6     .12       0
Bank Sta=4968.8,5018.6
XS Rating Curve= 0 ,0
Exp/Cntr=0.3,0.1

Type RM Length L Ch R = 1 ,8500    ,500,500,500
BEGIN DESCRIPTION:
FALL CREEK 17.0
END DESCRIPTION:
XS GIS Cut Line= 3
      2880905.68     10303203.16      2880936.27       10302826.
      2880755.68     10302303.11
#Sta/Elev= 30
  4621.6 1201.55  4651.7 1200.62  4685.2 1196.47  4802.2 1167.04  4807.2 1167.34
  4812.3 1163.68  4852.4 1150.02  4872.5 1148.29  4892.5 1148.63  4909.4  1146.1
  4910.4  1145.6  4959.2  1146.1  5034.5 1146.72  5049.2 1146.69  5087.7 1152.73
  5161.8 1159.73  5193.5  1167.2  5199.8 1170.59  5205.1  1170.6  5214.6 1173.42
    5231 1179.94  5236.3 1179.32  5299.3 1190.42  5405.1 1205.83    5444 1214.09
  5449.3  1212.9  5475.2 1219.05  5489.7 1221.11  5511.7 1221.36  5553.2 1226.38
#Mann= 4 ,-1 , 0
  4621.6     .05       0  4909.4     .03       0  4959.2     .05       0
  5034.5     .12       0
Bank Sta=4909.4,4959.2
XS Rating Curve= 0 ,0
Exp/Cntr=0.3,0.1