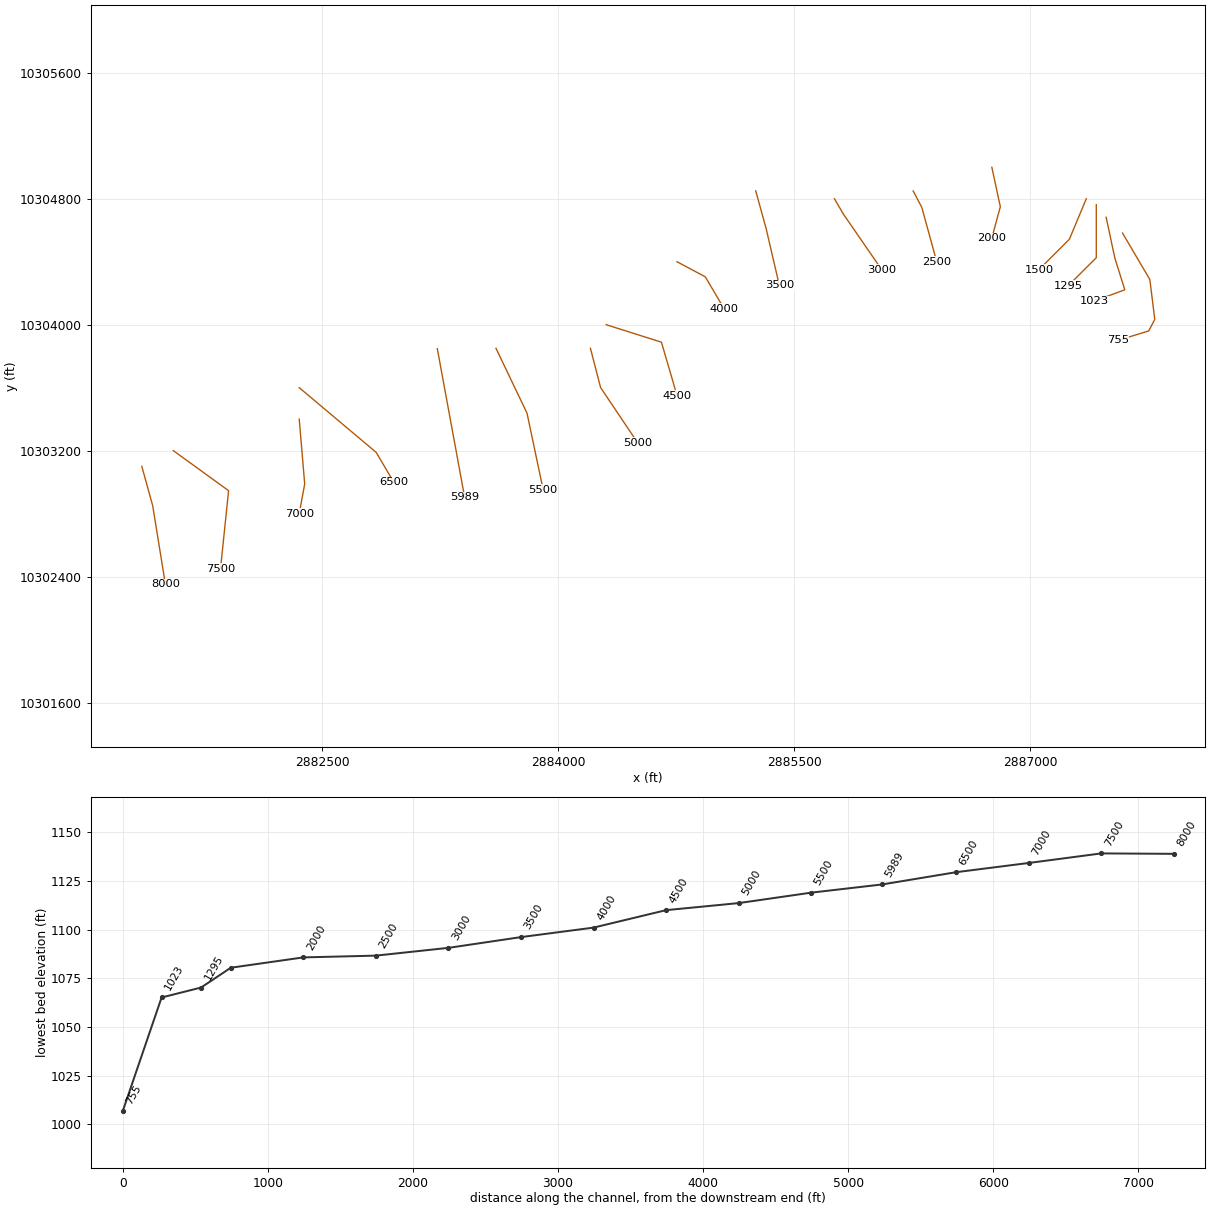
HEC-RAS study FALL CREEK.prj: FALL CREEK Base Level Engineering

--- FALL CREEK.g01 (geometry) --- (continued)

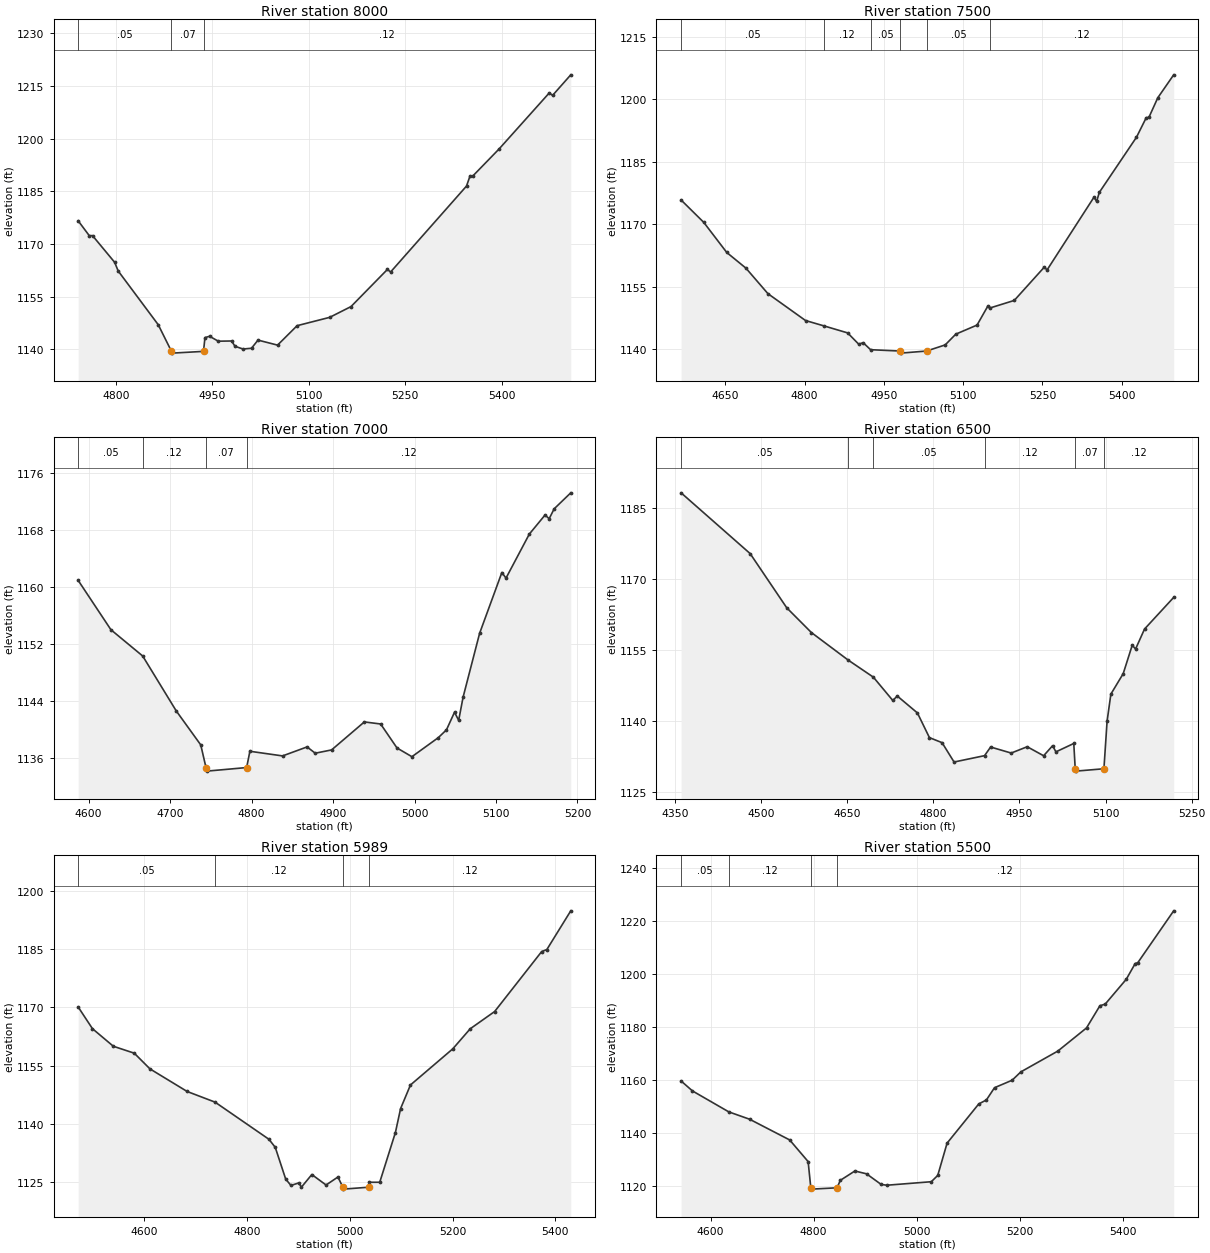
Type RM Length L Ch R = 1 ,8000    ,500,500,500
BEGIN DESCRIPTION:
FALL CREEK 16.0
END DESCRIPTION:
XS GIS Cut Line= 3
      2881355.69     10303103.11      2881424.56     10302854.05
      2881505.69     10302353.08
#Sta/Elev= 30
  4741.6  1176.6  4758.8 1172.38  4763.9 1172.38  4798.3 1164.78  4803.8 1162.31
  4866.1 1146.99  4886.7  1139.4  4887.7  1138.9  4936.5  1139.4  4938.7 1143.32
  4945.9  1143.7  4959.5  1142.3  4980.2 1142.36  4985.4 1140.85  4997.9 1140.07
  5011.1 1140.29  5021.2 1142.61  5051.6 1141.18    5082 1146.72  5132.6 1149.09
  5165.8 1152.16  5222.4 1162.74  5227.4 1162.02  5345.4  1186.5  5350.8 1189.34
  5355.8 1189.48    5396 1197.06  5474.1 1213.04  5479.2 1212.33  5507.5 1218.19
#Mann= 3 ,-1 , 0
  4741.6     .05       0  4886.7     .07       0  4936.5     .12       0
Bank Sta=4886.7,4936.5
XS Rating Curve= 0 ,0
Exp/Cntr=0.3,0.1

Type RM Length L Ch R = 1 ,7500    ,500,500,500
BEGIN DESCRIPTION:
FALL CREEK 15.0
END DESCRIPTION:
XS GIS Cut Line= 3
       2881555.7      10303203.1      2881906.94     10302948.69
      2881855.69     10302453.13
#Sta/Elev= 30
  4566.3 1175.85  4609.2 1170.48  4652.7 1163.26  4688.9 1159.51  4730.6 1153.38
  4801.7 1146.94  4836.6 1145.65  4881.4 1143.97  4902.3 1141.27  4910.8 1141.62
  4924.8 1139.94  4980.7 1139.62  4981.7 1139.12  5030.6 1139.62  5065.9 1141.09
    5086 1143.67  5126.2 1145.85  5146.4 1150.36  5151.2 1149.97  5196.6 1151.76
  5253.6 1159.77  5258.6 1159.06  5347.4 1176.52  5352.4 1175.51  5357.5 1177.67
  5427.8  1190.9  5446.3  1195.6  5451.3 1195.66  5468.1 1200.36  5498.2 1205.87
#Mann= 6 ,-1 , 0
  4566.3     .05       0  4836.6     .12       0  4924.8     .05       0
  4980.7     .03       0  5030.6     .05       0  5151.2     .12       0
Bank Sta=4980.7,5030.6
XS Rating Curve= 0 ,0
Exp/Cntr=0.3,0.1

Type RM Length L Ch R = 1 ,7000    ,500,500,500
BEGIN DESCRIPTION:
FALL CREEK 14.0
END DESCRIPTION:
XS GIS Cut Line= 3
      2882355.68     10303403.12      2882390.46     10302991.69
      2882355.68     10302803.07
#Sta/Elev= 30
  4587.1 1160.92  4627.3 1154.01  4666.3 1150.33  4707.5 1142.64  4737.6 1137.88
    4744 1134.71    4745 1134.21  4793.9 1134.71  4797.9 1136.99    4838 1136.34
  4868.1  1137.6  4878.1 1136.72  4898.2 1137.18  4938.4  1141.1  4958.4 1140.81
  4978.5 1137.45  4996.8 1136.23  5029.1 1138.89  5039.2 1139.99  5049.1 1142.46
  5054.2 1141.32  5059.6 1144.56  5079.9 1153.51  5107.2 1162.02  5112.3 1161.24
  5140.9  1167.4  5160.2 1170.07  5165.3 1169.56  5171.4 1170.94  5191.8 1173.18
#Mann= 4 ,-1 , 0
  4587.1     .05       0  4666.3     .12       0    4744     .07       0
  4793.9     .12       0
Bank Sta=4744,4793.9
XS Rating Curve= 0 ,0
Exp/Cntr=0.3,0.1

Type RM Length L Ch R = 1 ,6500    ,511,511,511
BEGIN DESCRIPTION:
FALL CREEK 13.0
END DESCRIPTION:
XS GIS Cut Line= 3
      2882355.71     10303603.09      2882844.98     10303191.61
      2882955.68     10303003.11
#Sta/Elev= 30
  4360.7 1188.13    4481 1175.32  4544.7  1163.9  4587.6 1158.69  4651.6 1152.89
  4695.6 1149.28  4729.4 1144.37  4737.2 1145.31  4772.3 1141.74  4793.2 1136.54
  4815.2 1135.48  4836.1  1131.4  4889.2 1132.74  4899.8 1134.56  4935.6 1133.29
  4963.5 1134.62  4992.1 1132.72  5007.7 1134.84  5013.5 1133.54  5044.6 1135.31
  5047.1 1129.98  5048.1 1129.48  5097.1 1129.98  5102.6 1139.99  5109.2 1145.71
  5130.7 1150.03  5146.4 1156.02  5152.2 1155.21  5167.8 1159.42  5218.6 1166.09
#Mann= 6 ,-1 , 0
  4360.7     .05       0  4651.6     .12       0  4695.6     .05       0
  4889.2     .12       0  5047.1     .07       0  5097.1     .12       0
Bank Sta=5047.1,5097.1
XS Rating Curve= 0 ,0
Exp/Cntr=0.3,0.1

Type RM Length L Ch R = 1 ,5989    ,489,489,489
BEGIN DESCRIPTION:
Mapping XS dedf339b
END DESCRIPTION:
XS GIS Cut Line= 2
      2883232.97     10303850.49      2883406.43     10302907.31
#Sta/Elev= 30
    4471 1170.09  4498.8  1164.5  4539.5 1159.97  4580.2 1158.19  4610.7 1154.15
  4683.2 1148.32  4737.5 1145.58  4842.4 1136.01  4854.7 1133.93    4875 1125.76
  4885.2 1124.12  4900.6 1124.77  4905.6 1123.67  4925.9 1126.93  4953.6 1124.23
  4976.7 1126.29  4986.3 1123.67  4987.3 1123.17  5037.2 1123.67  5037.7 1124.94
  5058.1 1124.94  5088.6 1137.75  5098.7 1143.92  5117.9    1150  5200.4 1159.32
  5234.2 1164.47  5281.8 1168.92  5373.3 1184.36  5383.4 1184.88    5430 1194.86
#Mann= 4 ,-1 , 0
    4471     .05       0  4737.5     .12       0  4986.3     .07       0
  5037.2     .12       0
Bank Sta=4986.3,5037.2
XS Rating Curve= 0 ,0
Exp/Cntr=0.3,0.1

Type RM Length L Ch R = 1 ,5500    ,500,500,500
BEGIN DESCRIPTION:
FALL CREEK 11.0
END DESCRIPTION:
XS GIS Cut Line= 3
       2883605.7     10303853.08      2883802.88     10303440.69
      2883905.68     10302953.11
#Sta/Elev= 30
  4542.9 1159.68    4565 1155.93  4635.5 1148.04  4675.9 1145.27  4753.5 1137.48
  4789.3 1129.33  4794.5 1119.46  4795.5 1118.96  4845.4 1119.46  4851.7 1122.27
    4880 1125.79  4902.6 1124.72  4930.9 1120.73  4941.9 1120.43  5028.2 1121.75
  5040.7 1124.13  5058.8 1136.28  5120.2 1151.03  5135.1 1152.55  5150.8 1157.15
  5184.9 1159.96  5201.9 1163.11  5273.5 1170.93  5329.2 1179.65  5355.2 1188.01
  5365.4 1188.61  5406.3 1197.97  5423.6 1203.89  5428.7 1204.23  5498.3 1223.75
#Mann= 4 ,-1 , 0
  4542.9     .05       0  4635.5     .12       0  4794.5     .07       0
  4845.4     .12       0
Bank Sta=4794.5,4845.4
XS Rating Curve= 0 ,0
Exp/Cntr=0.3,0.1

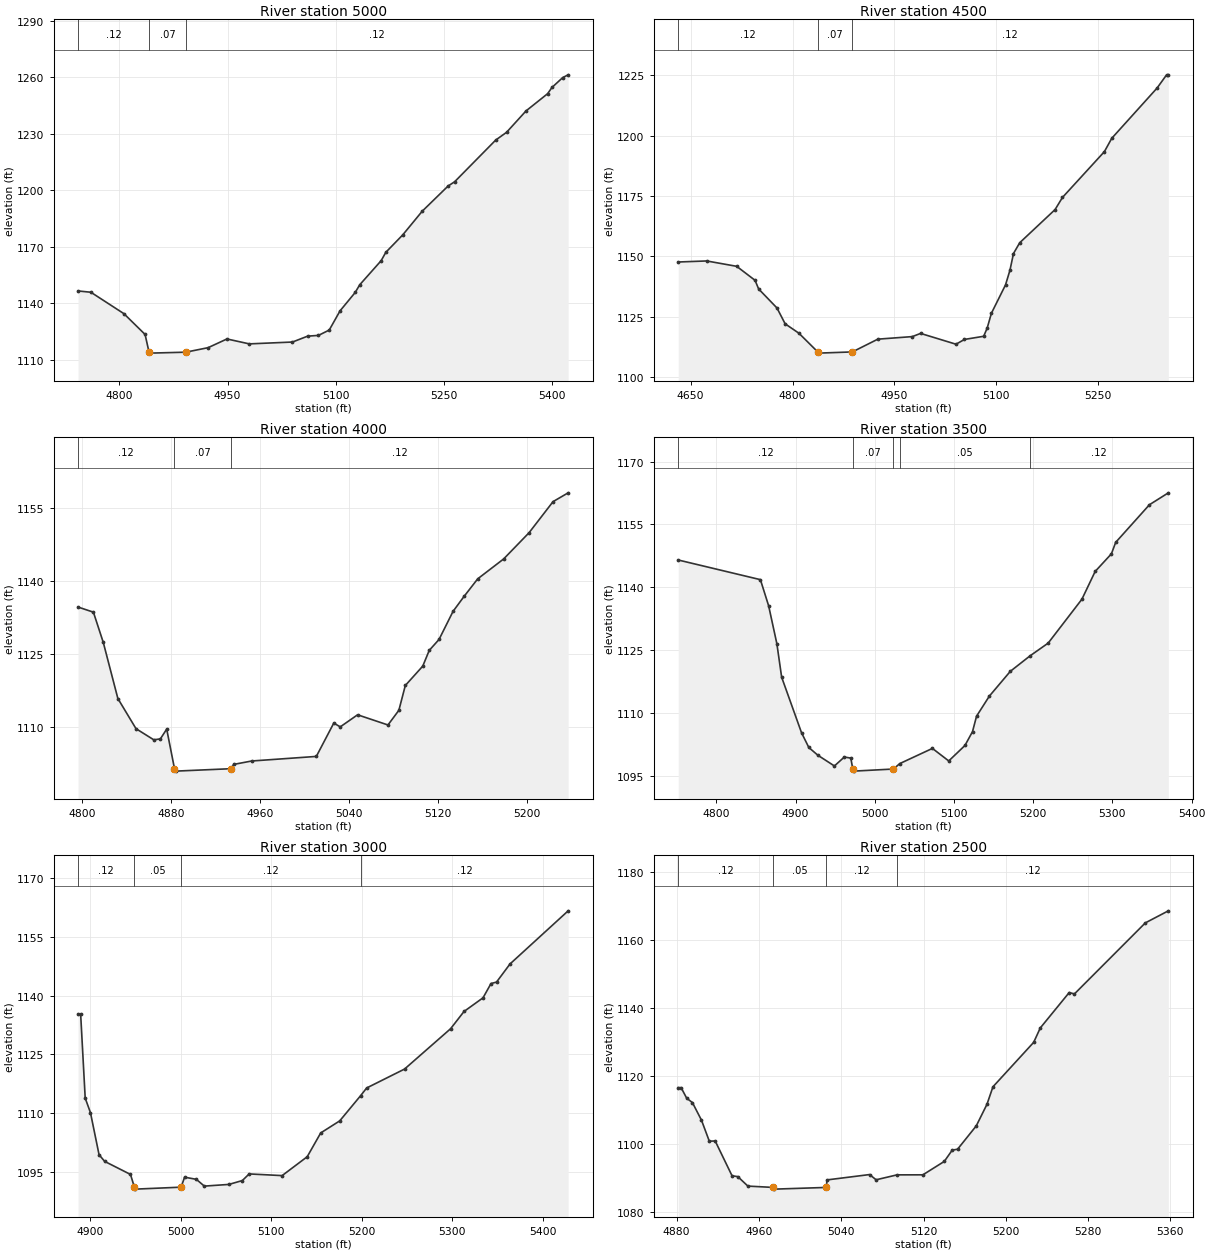
Type RM Length L Ch R = 1 ,5000    ,500,500,500
BEGIN DESCRIPTION:
FALL CREEK 10.0
END DESCRIPTION:
XS GIS Cut Line= 3
      2884205.67     10303853.15      2884270.03     10303603.93
      2884505.67     10303253.13
#Sta/Elev= 30
  4742.6  1146.6  4760.4 1145.92  4806.2 1134.55  4835.6 1123.51  4841.1 1114.09
  4842.1 1113.59    4892 1114.09    4923 1116.48  4949.2 1121.11  4980.2  1118.5
  5040.1 1119.48  5061.2 1122.61  5076.1    1123  5091.1 1125.84  5106.1 1136.04
  5127.1  1145.8  5133.5 1149.92  5163.1 1162.67  5169.6 1167.11  5193.1 1176.38
  5220.1 1188.94  5256.1 1202.35  5265.1 1204.59  5322.1 1226.73  5337.1 1230.83
  5364.1 1242.19  5394.1 1251.35  5400.1 1254.65  5415.1 1259.92  5422.6 1261.36
#Mann= 3 ,-1 , 0
  4742.6     .12       0  4841.1     .07       0    4892     .12       0
Bank Sta=4841.1,4892
XS Rating Curve= 0 ,0
Exp/Cntr=0.3,0.1

Type RM Length L Ch R = 1 ,4500    ,500,500,500
BEGIN DESCRIPTION:
FALL CREEK 9.0
END DESCRIPTION:
XS GIS Cut Line= 3
       2884305.7     10304003.11      2884656.73     10303891.98
      2884755.68     10303553.13
#Sta/Elev= 30
  4631.8 1147.69  4673.7 1148.12  4717.8  1145.9  4744.8 1140.11  4750.1 1136.53
  4777.1 1128.65  4789.1  1122.1  4809.4  1118.2  4837.1 1110.47  4838.1 1109.97
    4888 1110.47  4925.5 1115.75  4976.2 1116.81  4988.4 1118.13  5040.5 1113.66
    5053 1115.64  5081.2 1116.94  5086.4 1120.33  5092.6 1126.47  5113.4 1138.23
  5119.9  1144.3  5125.1  1151.2  5134.3 1155.67  5186.3 1169.39  5197.2 1174.42
  5258.9 1193.38  5269.7 1198.89  5336.3 1219.66  5350.4 1225.16    5353 1225.16
#Mann= 3 ,-1 , 0
  4631.8     .12       0  4837.1     .07       0    4888     .12       0
Bank Sta=4837.1,4888
XS Rating Curve= 0 ,0
Exp/Cntr=0.3,0.1

Type RM Length L Ch R = 1 ,4000    ,500,500,500
BEGIN DESCRIPTION:
FALL CREEK 8.0
END DESCRIPTION:
XS GIS Cut Line= 3
      2884755.66     10304403.13      2884935.42     10304307.09
      2885055.68     10304103.11
#Sta/Elev= 30
  4796.2  1134.7    4810 1133.65  4818.9 1127.42    4832 1115.91  4848.3 1109.72
  4864.3 1107.43  4870.2 1107.62  4875.9 1109.63  4882.9  1101.5  4883.9    1101
  4933.9  1101.5  4936.1 1102.38  4952.3 1103.08  5010.4 1104.02  5026.1 1110.87
  5031.9 1110.09  5047.5 1112.57  5074.8 1110.48  5084.6 1113.49  5090.4 1118.59
  5106.1 1122.57  5111.9  1125.8  5120.7 1128.04  5133.3 1133.81  5143.2 1136.88
  5155.5  1140.5  5178.8 1144.58  5201.7 1149.98  5223.2 1156.35  5236.8 1158.16
#Mann= 3 ,-1 , 0
  4796.2     .12       0  4882.9     .07       0  4933.9     .12       0
Bank Sta=4882.9,4933.9
XS Rating Curve= 0 ,0
Exp/Cntr=0.3,0.1

Type RM Length L Ch R = 1 ,3500    ,500,500,500
BEGIN DESCRIPTION:
FALL CREEK 7.0
END DESCRIPTION:
XS GIS Cut Line= 3
      2885255.69     10304853.09      2885321.75     10304614.04
      2885405.69     10304253.08
#Sta/Elev= 30
    4752  1146.5  4855.7 1141.81  4866.1 1135.56  4876.5  1126.5  4882.5 1118.54
  4907.6 1105.28  4916.8 1101.76  4928.3  1099.9  4949.1 1097.35  4961.6 1099.48
  4969.8 1099.23  4972.3 1096.62  4973.3 1096.12  5023.6 1096.62  5031.6 1097.92
  5072.8 1101.54  5093.4 1098.55  5113.9 1102.25  5123.4 1105.55  5128.5 1109.23
  5144.7 1114.03  5171.1 1119.93  5196.1 1123.64  5218.9 1126.67  5261.5 1137.15
  5278.2 1143.77  5298.7 1147.97  5304.1 1150.71  5346.7 1159.69  5370.6 1162.53
#Mann= 5 ,-1 , 0
    4752     .12       0  4972.3     .07       0  5023.6     .12       0
  5031.6     .05       0  5196.1     .12       0
Bank Sta=4972.3,5023.6
XS Rating Curve= 0 ,0
Exp/Cntr=0.3,0.1

Type RM Length L Ch R = 1 ,3000    ,500,500,500
BEGIN DESCRIPTION:
FALL CREEK 6.0
END DESCRIPTION:
XS GIS Cut Line= 3
      2885755.67     10304803.13      2885812.82     10304705.41
      2886055.68     10304353.11
#Sta/Elev= 30
  4886.8 1135.18  4889.7 1135.18  4894.7 1113.83  4900.5 1110.12    4910 1099.38
  4916.2 1097.68  4944.7 1094.35    4949  1091.1    4950  1090.6  5000.6  1091.1
  5004.4 1093.65  5017.4  1093.1  5026.2 1091.37  5053.3  1091.8  5068.2 1092.79
  5075.7 1094.48  5112.1 1094.05  5139.8 1098.87  5154.7 1104.94  5175.7 1108.02
  5198.9 1114.49  5205.4 1116.41  5247.3 1121.25  5298.1 1131.54  5312.9 1135.94
  5333.9 1139.43  5342.7 1143.07  5348.8 1143.44  5363.7 1148.07  5427.9 1161.63
#Mann= 4 ,-1 , 0
  4886.8     .12       0    4949     .05       0  5000.6     .12       0
  5198.9     .12       0
Bank Sta=4949,5000.6
XS Rating Curve= 0 ,0
Exp/Cntr=0.3,0.1

Type RM Length L Ch R = 1 ,2500    ,500,500,500
BEGIN DESCRIPTION:
FALL CREEK 5.0
END DESCRIPTION:
XS GIS Cut Line= 3
       2886255.7     10304853.08      2886310.77     10304748.26
      2886405.69     10304403.08
#Sta/Elev= 30
  4881.6 1116.48  4884.4 1116.48  4889.8 1113.38  4895.4 1112.08  4904.2  1106.9
  4911.8 1100.72  4917.5 1100.79  4933.9 1090.54  4939.5 1090.29  4949.3  1087.5
  4974.1 1087.11  4975.1 1086.61  5025.7 1087.11  5026.1 1089.32  5067.6  1090.9
  5073.9 1089.36  5094.3 1090.81  5119.4 1090.82  5140.2 1094.77  5147.9 1098.09
  5153.1 1098.36  5171.3 1105.24  5181.7  1111.6  5187.5 1116.74  5227.1 1129.83
  5233.5 1134.06  5261.6 1144.48  5266.7 1144.08  5335.6 1164.99    5358 1168.54
#Mann= 4 ,-1 , 0
  4881.6     .12       0  4974.1     .05       0  5025.7     .12       0
  5094.3     .12       0
Bank Sta=4974.1,5025.7
XS Rating Curve= 0 ,0
Exp/Cntr=0.3,0.1

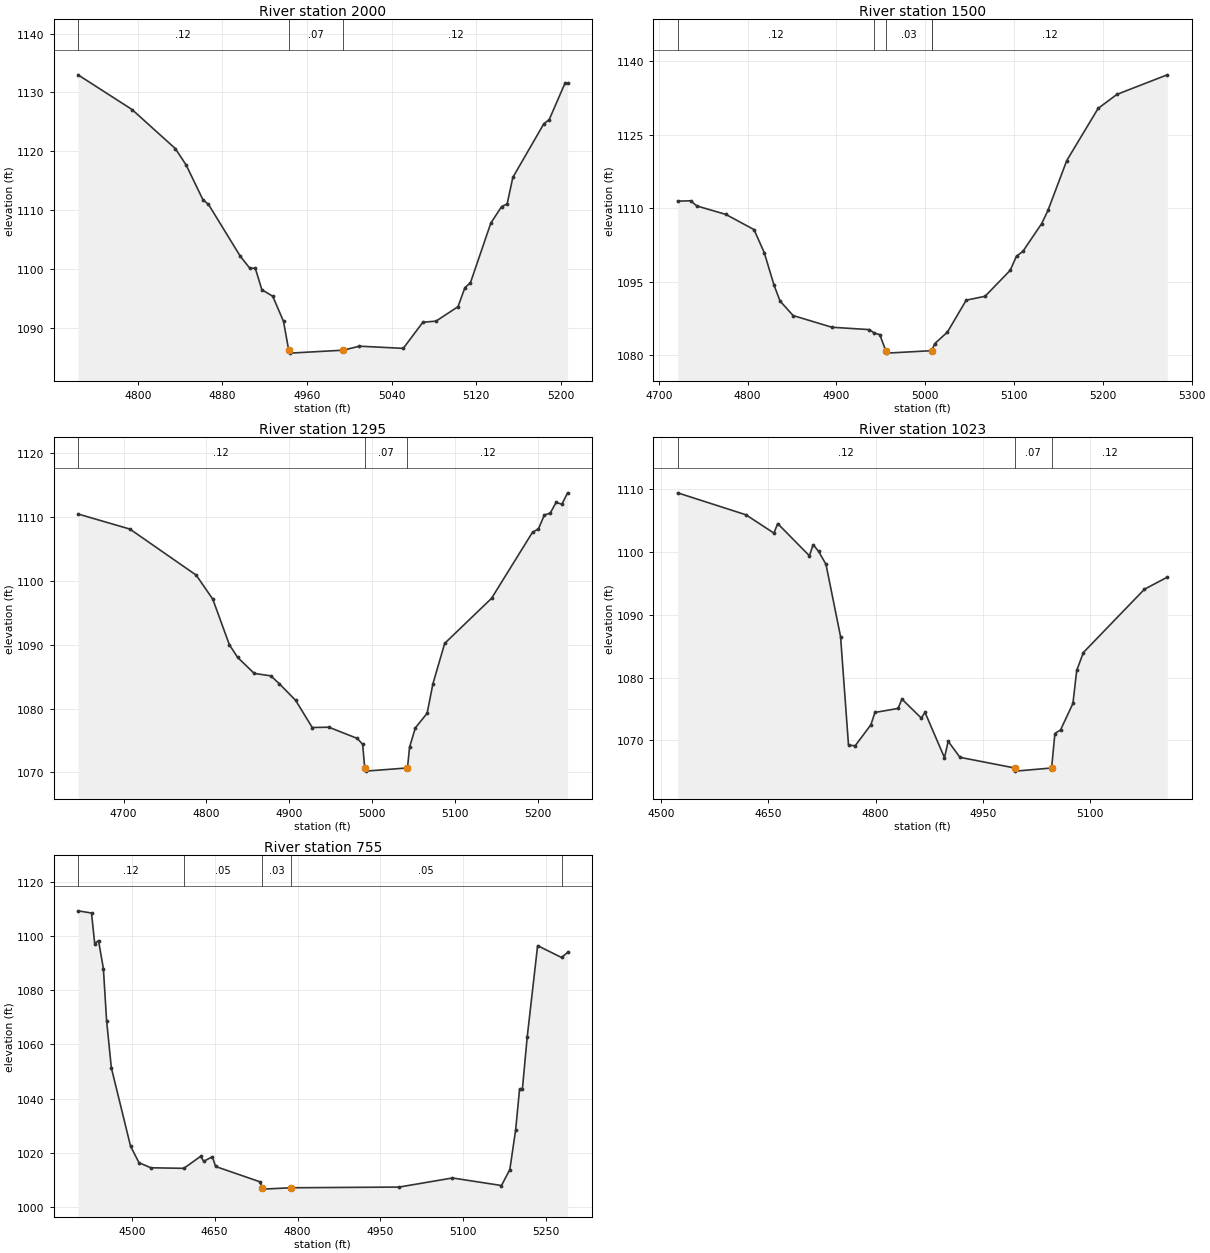
Type RM Length L Ch R = 1 ,2000    ,500,500,500
BEGIN DESCRIPTION:
FALL CREEK 4.0
END DESCRIPTION:
XS GIS Cut Line= 3
      2886755.69     10305003.07      2886809.63     10304752.31
      2886755.68     10304553.08
#Sta/Elev= 30
  4743.5 1132.99  4794.6 1127.09  4835.5 1120.46  4845.7 1117.68  4861.7 1111.73
  4866.8 1110.99  4896.9 1102.17    4906 1100.11  4911.1 1100.14  4917.3 1096.47
  4927.6 1095.37  4937.8 1091.09  4942.7  1086.2  4943.7  1085.7  4994.3  1086.2
  5009.5 1086.88    5051 1086.51  5069.5 1090.94    5082 1091.14  5102.8  1093.6
  5109.3 1096.83  5114.5 1097.65  5133.8  1107.8    5144 1110.61  5149.2 1111.04
  5154.6 1115.56  5183.9 1124.67    5189 1125.39  5203.8 1131.52  5206.4 1131.52
#Mann= 3 ,-1 , 0
  4743.5     .12       0  4942.7     .07       0  4994.3     .12       0
Bank Sta=4942.7,4994.3
XS Rating Curve= 0 ,0
Exp/Cntr=0.3,0.1

Type RM Length L Ch R = 1 ,1500    ,205,205,205
BEGIN DESCRIPTION:
FALL CREEK 3.0
END DESCRIPTION:
XS GIS Cut Line= 3
      2887355.68      10304803.1      2887248.23     10304545.95
      2887055.69     10304353.12
#Sta/Elev= 30
  4721.3 1111.41  4735.9 1111.48    4743 1110.42  4775.5 1108.71  4807.3  1105.6
  4818.8 1100.91  4829.7 1094.34  4836.5 1091.05  4851.3 1088.06    4895 1085.67
  4937.2 1085.19  4942.6  1084.5  4948.9 1084.16  4955.6 1080.89  4956.6 1080.39
  5007.2 1080.89  5007.9 1081.17  5010.9 1082.35    5025 1084.68  5046.2  1091.2
  5067.4 1091.99  5095.7 1097.29  5102.8 1100.19  5109.9 1101.14  5131.1 1106.82
  5138.2 1109.51  5159.4  1119.7  5194.7 1130.34  5215.9  1133.2  5272.5 1137.19
#Mann= 5 ,-1 , 0
  4721.3     .12       0  4942.6     .05       0  4955.6     .03       0
  5007.2     .05       0  5007.9     .12       0
Bank Sta=4955.6,5007.2
XS Rating Curve= 0 ,0
Exp/Cntr=0.3,0.1

Type RM Length L Ch R = 1 ,1295    ,272,272,272
BEGIN DESCRIPTION:
Mapping XS 95033f39
END DESCRIPTION:
XS GIS Cut Line= 3
      2887419.25     10304765.66      2887419.25     10304428.86
      2887239.71     10304249.33
#Sta/Elev= 30
  4645.1 1110.42  4707.7 1108.06  4787.7 1100.86  4807.7  1097.1  4827.7 1089.98
  4837.7 1087.99  4857.7 1085.49  4877.7 1085.11  4887.7 1083.91  4907.7 1081.27
  4927.7 1077.03  4947.7 1077.08  4981.9 1075.33  4988.5 1074.41    4991 1070.71
    4992 1070.21  5042.6 1070.71  5045.1 1073.96  5052.1 1076.98  5066.3 1079.26
  5073.3 1083.88  5087.5 1090.19    5144 1097.23  5193.5 1107.58  5200.6 1108.08
  5207.7 1110.26  5214.8 1110.55  5221.8 1112.22  5228.9 1111.96  5235.8 1113.73
#Mann= 3 ,-1 , 0
  4645.1     .12       0    4991     .07       0  5042.6     .12       0
Bank Sta=4991,5042.6
XS Rating Curve= 0 ,0
Exp/Cntr=0.3,0.1

Type RM Length L Ch R = 1 ,1023    ,268,268,268
BEGIN DESCRIPTION:
FALL CREEK 2.0
END DESCRIPTION:
XS GIS Cut Line= 4
      2887481.75     10304685.81       2887537.3     10304425.39
      2887600.48     10304224.68      2887405.71     10304153.12
#Sta/Elev= 30
  4523.3  1109.4  4618.6 1105.91  4657.9 1102.99  4663.1 1104.51  4707.5 1099.37
  4712.6 1101.15  4720.3 1100.08  4730.6 1098.02    4751  1086.5  4762.1 1069.22
  4771.5 1069.15  4793.4 1072.49    4799 1074.44  4831.4 1075.08  4836.7 1076.57
  4863.8 1073.55    4869 1074.45  4896.2 1067.24  4901.4 1069.85  4917.8  1067.3
  4994.3  1065.6  4995.3  1065.1  5045.9  1065.6  5050.5 1071.08  5058.4 1071.66
  5075.7 1075.87    5081 1081.13  5090.3 1083.98  5175.6 1094.05  5207.5 1095.97
#Mann= 3 ,-1 , 0
  4523.3     .12       0  4994.3     .07       0  5045.9     .12       0
Bank Sta=4994.3,5045.9
XS Rating Curve= 0 ,0
Exp/Cntr=0.3,0.1

Type RM Length L Ch R = 1 ,755     ,0,0,0
BEGIN DESCRIPTION:
FALL CREEK 1.0
END DESCRIPTION:
XS GIS Cut Line= 5
      2887585.92     10304585.11      2887759.52     10304289.97
      2887790.75       10304037.      2887752.58     10303963.58
       2887555.7     10303903.12
#Sta/Elev= 30
  4402.7 1109.22  4427.1 1108.41  4432.9 1097.16  4439.8 1098.28  4448.6 1087.92
  4454.4  1068.8    4463 1051.39  4497.8 1022.47    4513 1016.42  4534.4 1014.54
  4594.2 1014.33  4624.4 1018.73  4630.2 1016.92  4645.8 1018.61  4651.6 1015.02
  4731.7 1009.39  4736.3 1007.17  4737.3 1006.67  4787.9 1007.17  4983.8 1007.43
  5080.2 1010.78    5169    1008  5184.1 1013.88  5194.6  1028.4  5201.7 1043.46
  5206.9 1043.66  5215.5  1062.6  5234.4 1096.38  5277.7 1092.03  5288.7 1093.89
#Mann= 5 ,-1 , 0
  4402.7     .12       0  4594.2     .05       0  4736.3     .03       0
  4787.9     .05       0  5277.7     .12       0
Bank Sta=4736.3,4787.9
XS Rating Curve= 0 ,0
Exp/Cntr=0.3,0.1

Chan Stop Cuts=-1
Use User Specified Reach Order=0