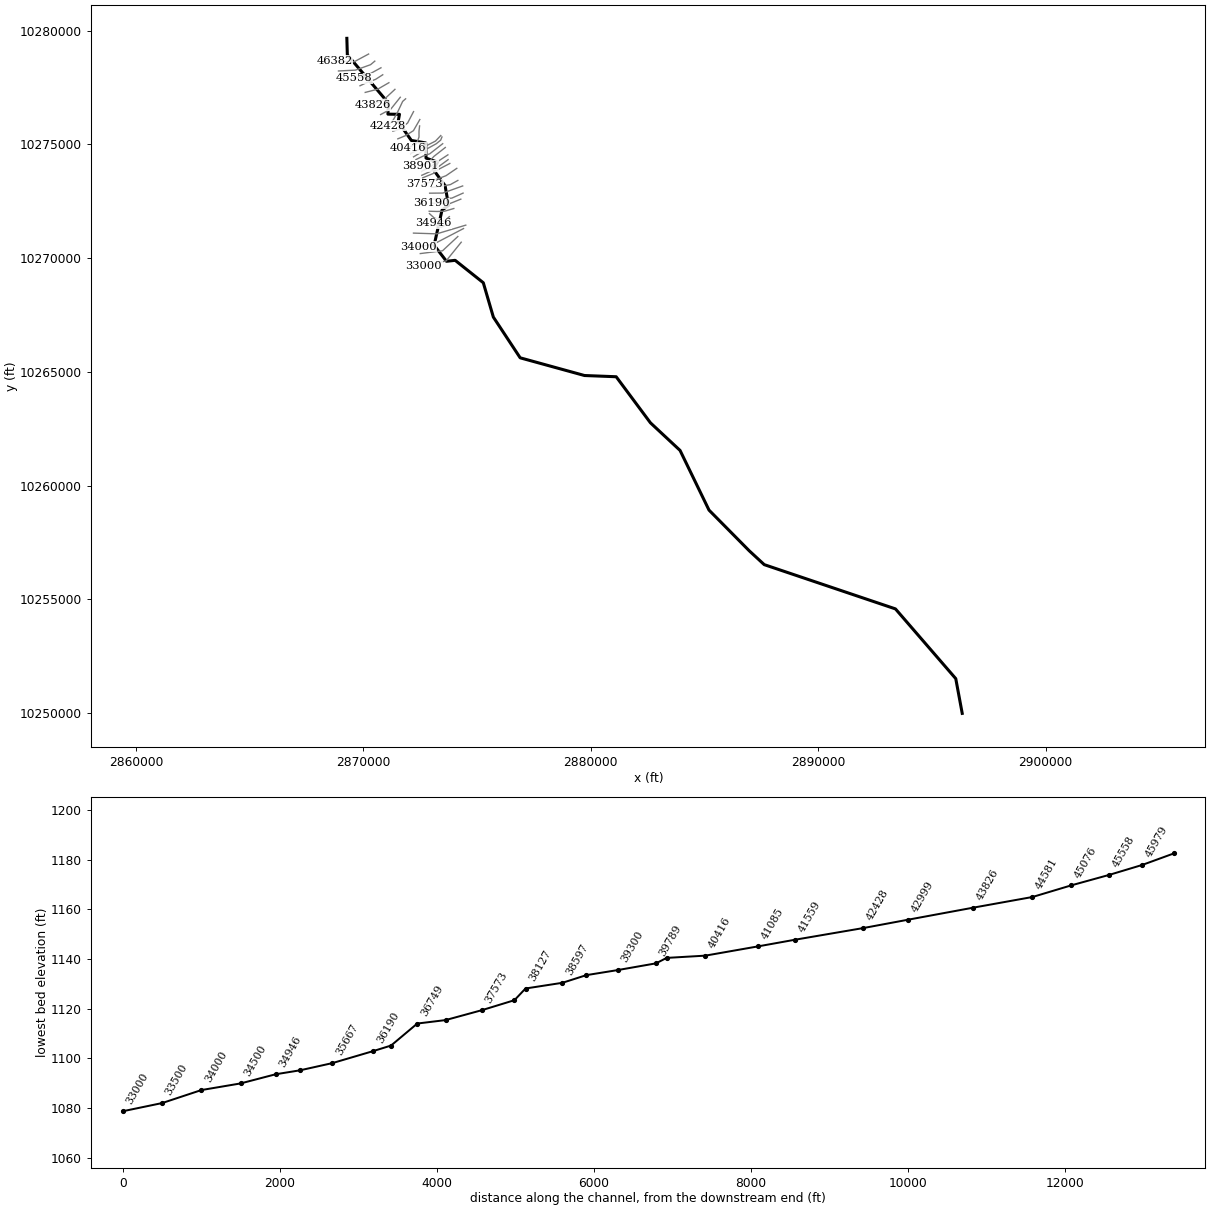
--- RED ROCK CREEK.prj (project) ---

Proj Title=RED ROCK CREEK Base Level Engineering
Current Plan=p01
Default Exp/Contr=0.3,0.1
English Units
Geom File=g01
Flow File=f01
Plan File=p01
Y Axis Title=Elevation
X Axis Title(PF)=Main Channel Distance
X Axis Title(XS)=Station
BEGIN DESCRIPTION:
RED ROCK CREEK
END DESCRIPTION:
DSS Export Rating Curves= 0
DSS Export Rating Curve Sorted= 0
DSS Export Volume Flow Curves= 0
DXF OffsetX= 0
DXF OffsetY= 0
DXF ScaleX= 1
DXF ScaleY= 10

--- RED ROCK CREEK.p01 (plan) ---

Plan Title=Multiple Run
Short Identifier=Multiple
Geom File=g01
Flow File=f01
Subcritical Flow
K Sum by GR= 0
Std Step Tol= 0.01
Critical Tol= 0.01
Num of Std Step Trials= 20
Max Error Tol= 0.3
Flow Tol Ratio= 0.001
Split Flow NTrial= 30
Split Flow Tol= 0.02
Split Flow Ratio= 0.02
Log Output Level= 0
Friction Slope Method= 1
Unsteady Friction Slope Method= 2
Unsteady Bridges Friction Slope Method= 1
Parabolic Critical Depth
Global Vel Dist=  1 , 1 , 1
Global Log Level= 0
CheckData=True
Encroach Param= -1, 0, 0, 0
BEGIN DESCRIPTION:
Multiple Run
END DESCRIPTION:

--- RED ROCK CREEK.f01 (steady flow) ---

Flow Title=Multiple
Number of Profiles=7
Profile Names=10-year,25-year,50-year,1pct_min,100-year,1pct_plu,500-year
River Rch & RM= RED ROCK CREEK,Reach-1,46382
     584     977    1087     719    1442    2895    1967
River Rch & RM= RED ROCK CREEK,Reach-1,33500
     896    1539    1794    1169    2421    5013    3293
River Rch & RM= RED ROCK CREEK,Reach-1,27000
    1423    2495    3321    2232    4579    9393    6208
River Rch & RM= RED ROCK CREEK,Reach-1,23500
    1594    2812    3770    2530    5215   10748    7054
River Rch & RM= RED ROCK CREEK,Reach-1,22000
    1800    3202    4228    2801    5858   12253    7902
River Rch & RM= RED ROCK CREEK,Reach-1,18500
    2017    3618    4680    3062    6492   13764    8726
Boundary for River Rch & Prof#=RED ROCK CREEK,Reach-1,1
Up Type=0
Dn Type=3
Dn Slope=0.005
Boundary for River Rch & Prof#=RED ROCK CREEK,Reach-1,2
Up Type=0
Dn Type=3
Dn Slope=0.005
Boundary for River Rch & Prof#=RED ROCK CREEK,Reach-1,3
Up Type=0
Dn Type=3
Dn Slope=0.005
Boundary for River Rch & Prof#=RED ROCK CREEK,Reach-1,4
Up Type=0
Dn Type=3
Dn Slope=0.005
Boundary for River Rch & Prof#=RED ROCK CREEK,Reach-1,5
Up Type=0
Dn Type=3
Dn Slope=0.005
Boundary for River Rch & Prof#=RED ROCK CREEK,Reach-1,6
Up Type=0
Dn Type=3
Dn Slope=0.005
Boundary for River Rch & Prof#=RED ROCK CREEK,Reach-1,7
Up Type=0
Dn Type=3
Dn Slope=0.005

--- RED ROCK CREEK.g01 (geometry) ---

Geom Title=Existing Conditions
Program Version=4.00

River Reach=RED ROCK CREEK  ,Reach-1
Reach XY= 30
      2869276.75       10279666.        2869298.       10278941.
       2871097.5       10276830.      2871083.25       10276333.
        2871590.       10276325.      2871530.25       10275999.
      2872113.75       10275176.      2872742.75       10275068.
       2872757.5       10274401.       2873261.5       10274222.
        2873074.       10273904.      2873594.75       10273189.
        2873749.       10272322.       2873461.5       10272116.
      2873113.75       10270570.       2873657.5       10269864.
      2874038.25       10269906.       2875275.5       10268921.
      2875717.75       10267410.        2876897.       10265620.
      2879724.75       10264842.      2881117.75       10264788.
       2882623.5       10262763.      2883926.75       10261548.
      2885198.75       10258925.      2886971.75       10257132.
       2887627.5       10256527.        2893397.       10254581.
       2896047.5       10251515.      2896331.25       10249988.

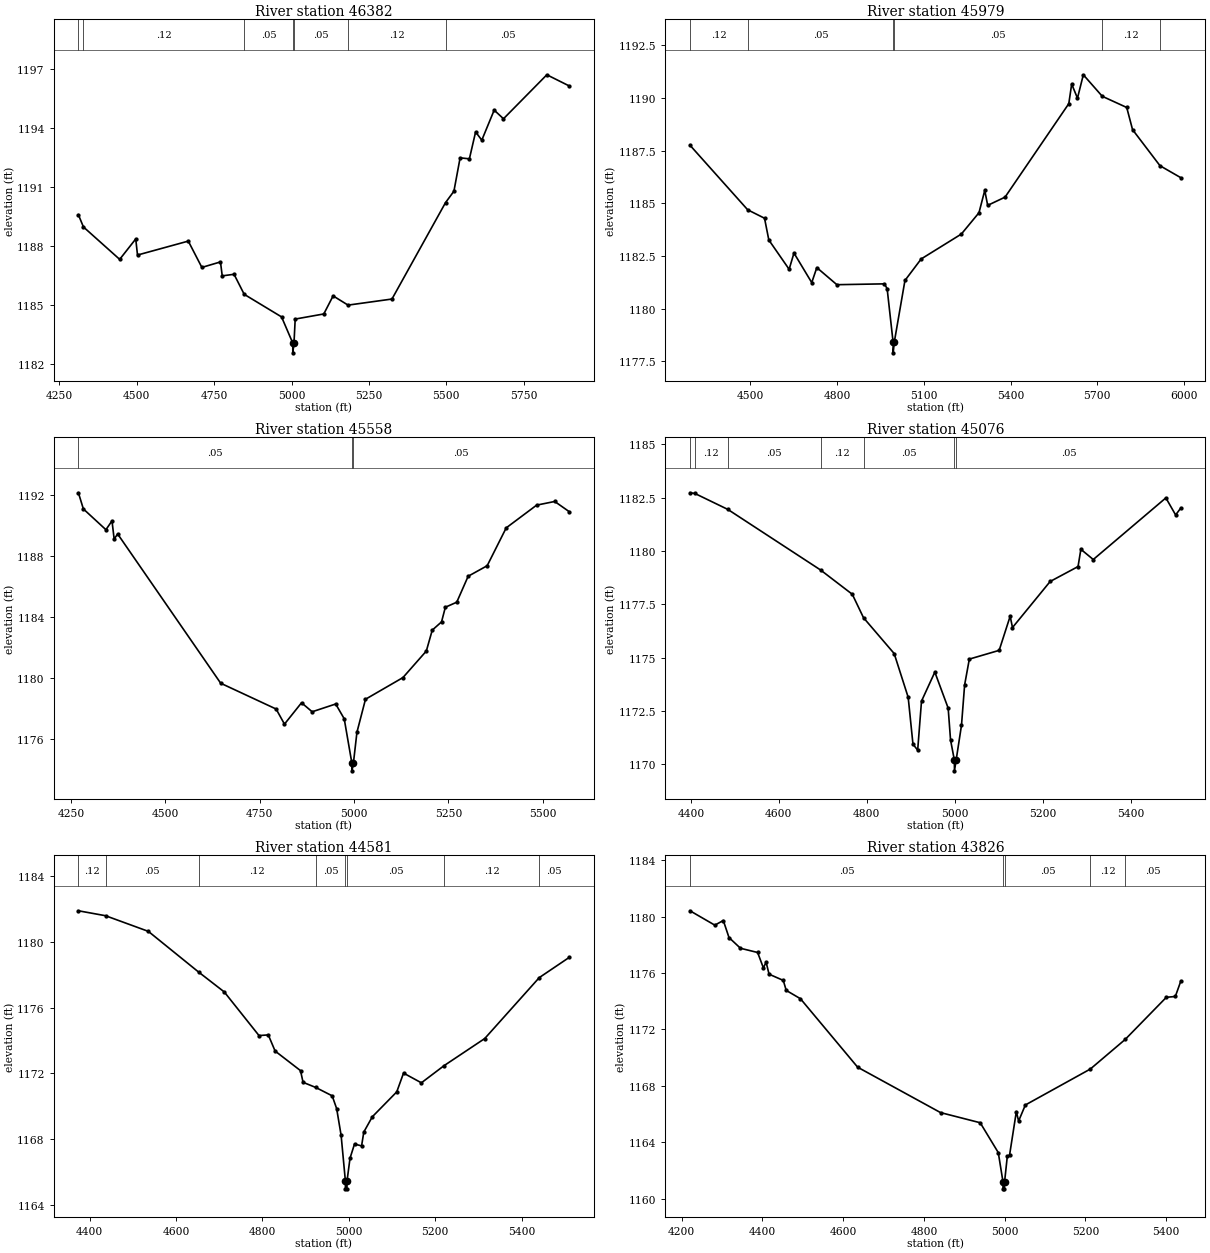
Type RM Length L Ch R = 1 ,46382   ,403,403,403
BEGIN DESCRIPTION:
RED ROCK CREEK 83.0
END DESCRIPTION:
XS GIS Cut Line= 3
      2870233.23     10278976.09      2869598.38      10278635.9
      2868733.27      10278676.1
#Sta/Elev= 30
  4311.2 1189.59  4327.5 1188.97  4444.6 1187.32  4496.5 1188.36  4502.2 1187.54
  4666.3 1188.25  4710.2 1186.91  4770.3 1187.19    4776 1186.48  4814.2 1186.56
    4847 1185.54  4967.7 1184.39  5003.9 1183.06  5004.1 1182.56  5007.9 1183.06
  5011.8 1184.28  5104.2 1184.54  5134.3 1185.46  5182.6 1184.99  5324.5  1185.3
  5497.6 1190.21  5524.7 1190.79  5544.7 1192.49  5574.7 1192.44  5594.8 1193.81
  5614.8 1193.39  5654.8 1194.92  5684.9 1194.48    5825 1196.72  5897.5 1196.15
#Mann= 7 ,-1 , 0
  4311.2     .05       0  4327.5     .12       0    4847     .05       0
  5003.9     .05       0  5007.9     .05       0  5182.6     .12       0
  5497.6     .05       0
Bank Sta=5003.9,5007.9
XS Rating Curve= 0 ,0
Exp/Cntr=0.3,0.1

Type RM Length L Ch R = 1 ,45979   ,421,421,421
BEGIN DESCRIPTION:
Mapping XS 68e3e9cc
END DESCRIPTION:
XS GIS Cut Line= 4
      2870505.95     10278663.56      2870318.49     10278507.34
      2869651.82     10278267.76      2868908.84     10278231.39
#Sta/Elev= 30
  4292.4 1187.75  4491.8 1184.69    4550 1184.29  4564.8 1183.26    4635 1181.87
  4651.7 1182.64  4713.1 1181.24  4730.7 1181.95    4800 1181.14  4964.4 1181.18
  4973.7 1180.95  4994.3 1178.41  4994.6 1177.91  4998.3 1178.41  5035.2 1181.34
  5091.3 1182.36  5230.1 1183.54    5291 1184.55    5311 1185.61  5321.1  1184.9
  5381.1 1185.29  5601.4 1189.72  5611.4 1190.65  5631.4 1189.98  5651.6 1191.09
  5717.1 1190.07  5801.6 1189.54  5821.7 1188.49  5916.5 1186.78  5988.7 1186.21
#Mann= 6 ,-1 , 0
  4292.4     .12       0  4491.8     .05       0  4994.3     .05       0
  4998.3     .05       0  5717.1     .12       0  5916.5     .05       0
Bank Sta=4994.3,4998.3
XS Rating Curve= 0 ,0
Exp/Cntr=0.3,0.1

Type RM Length L Ch R = 1 ,45558   ,482,482,482
BEGIN DESCRIPTION:
Mapping XS 14ca9b57
END DESCRIPTION:
XS GIS Cut Line= 4
      2870776.85     10278371.94      2870302.87     10278111.51
      2870000.78     10277965.67      2869579.84     10277913.71
#Sta/Elev= 30
  4269.7 1192.12  4282.9 1191.06  4342.6  1189.7  4358.7 1190.28  4364.4 1189.09
  4373.7 1189.42  4646.7 1179.64  4793.5 1177.95  4815.6 1176.96  4860.8 1178.36
    4889 1177.77  4951.3 1178.28  4973.9 1177.31  4994.2  1174.4  4994.4  1173.9
  4998.2  1174.4  5007.6 1176.43  5030.2 1178.59  5129.4 1180.01  5191.4 1181.75
  5207.1 1183.12  5231.7 1183.66  5241.8 1184.62    5272 1184.95  5302.2 1186.65
  5352.6 1187.34    5403 1189.82  5483.6 1191.31  5531.5 1191.55  5570.1 1190.88
#Mann= 3 ,-1 , 0
  4269.7     .05       0  4994.2     .03       0  4998.2     .05       0
Bank Sta=4994.2,4998.2
XS Rating Curve= 0 ,0
Exp/Cntr=0.3,0.1

Type RM Length L Ch R = 1 ,45076   ,495,495,495
BEGIN DESCRIPTION:
Mapping XS 90226a8f
END DESCRIPTION:
XS GIS Cut Line= 4
      2870854.91     10278064.61      2870537.24     10277861.51
      2870104.95     10277700.05      2869854.97     10277580.27
#Sta/Elev= 30
    4398 1182.73  4408.9  1182.7    4484 1181.95  4694.7 1179.11  4766.9 1177.97
  4792.4 1176.87  4862.1 1175.19  4893.9 1173.14  4904.8 1170.94  4915.5 1170.66
  4924.2 1172.96  4954.5 1174.32  4984.8 1172.63  4990.2 1171.14  4998.9 1170.19
  4999.1 1169.69  5002.9 1170.19  5015.1 1171.83  5022.2 1173.72  5032.9 1174.93
  5100.7 1175.34  5125.7 1176.94    5131 1176.41  5216.6 1178.57    5280 1179.27
  5286.4 1180.08  5314.6  1179.6  5479.6 1182.49  5501.8 1181.69  5513.7 1182.02
#Mann= 7 ,-1 , 0
    4398     .05       0  4408.9     .12       0    4484     .05       0
  4694.7     .12       0  4792.4     .05       0  4998.9     .03       0
  5002.9     .05       0
Bank Sta=4998.9,5002.9
XS Rating Curve= 0 ,0
Exp/Cntr=0.3,0.1

Type RM Length L Ch R = 1 ,44581   ,755,755,755
BEGIN DESCRIPTION:
Mapping XS 73488c2f
END DESCRIPTION:
XS GIS Cut Line= 3
      2871125.78     10277715.68      2870630.99     10277429.22
      2870084.12     10277288.59
#Sta/Elev= 30
    4374 1181.88  4436.8 1181.58  4535.9 1180.63  4652.2 1178.16  4711.7 1176.95
  4792.1  1174.3  4813.6 1174.34  4829.4 1173.36  4888.2 1172.17  4894.1 1171.46
  4923.3 1171.15  4961.5 1170.64  4971.9 1169.86  4982.2 1168.24    4992 1165.49
  4992.2 1164.99  4995.7 1164.99    4996 1165.49  5002.8 1166.85  5013.2 1167.71
  5029.6  1167.6  5034.7 1168.44  5054.5 1169.37    5111 1170.88  5126.7 1172.02
    5168 1171.43  5220.4 1172.47  5314.7 1174.12  5440.9 1177.82  5510.4 1179.05
#Mann= 8 ,-1 , 0
    4374     .12       0  4436.8     .05       0  4652.2     .12       0
  4923.3     .05       0    4992     .05       0    4996     .05       0
  5220.4     .12       0  5440.9     .05       0
Bank Sta=4992,4996
XS Rating Curve= 0 ,0
Exp/Cntr=0.3,0.1

Type RM Length L Ch R = 1 ,43826   ,827,827,827
BEGIN DESCRIPTION:
Mapping XS 89fe37d6
END DESCRIPTION:
XS GIS Cut Line= 3
      2871391.38     10277423.98      2870943.49     10277007.34
      2870403.45     10276737.32
#Sta/Elev= 30
  4220.7 1180.42  4282.2  1179.4  4303.2 1179.73  4317.3 1178.52  4345.7 1177.76
  4388.2 1177.46  4402.4 1176.37  4409.2 1176.77  4416.5 1175.92  4451.7 1175.48
    4459 1174.77  4494.2 1174.18  4635.9 1169.32  4841.1  1166.1  4939.3 1165.38
  4984.1 1163.26  4995.7 1161.19  4995.9 1160.69  4999.4 1160.69  4999.7 1161.19
  5006.4 1162.99    5012 1163.08  5028.8 1166.17  5034.4  1165.5  5051.1 1166.64
    5212 1169.19  5298.3 1171.29  5400.2 1174.28  5422.5 1174.34  5436.2 1175.44
#Mann= 5 ,-1 , 0
  4220.7     .05       0  4995.7     .05       0  4999.7     .05       0
    5212     .12       0  5298.3     .05       0
Bank Sta=4995.7,4999.7
XS Rating Curve= 0 ,0
Exp/Cntr=0.3,0.1

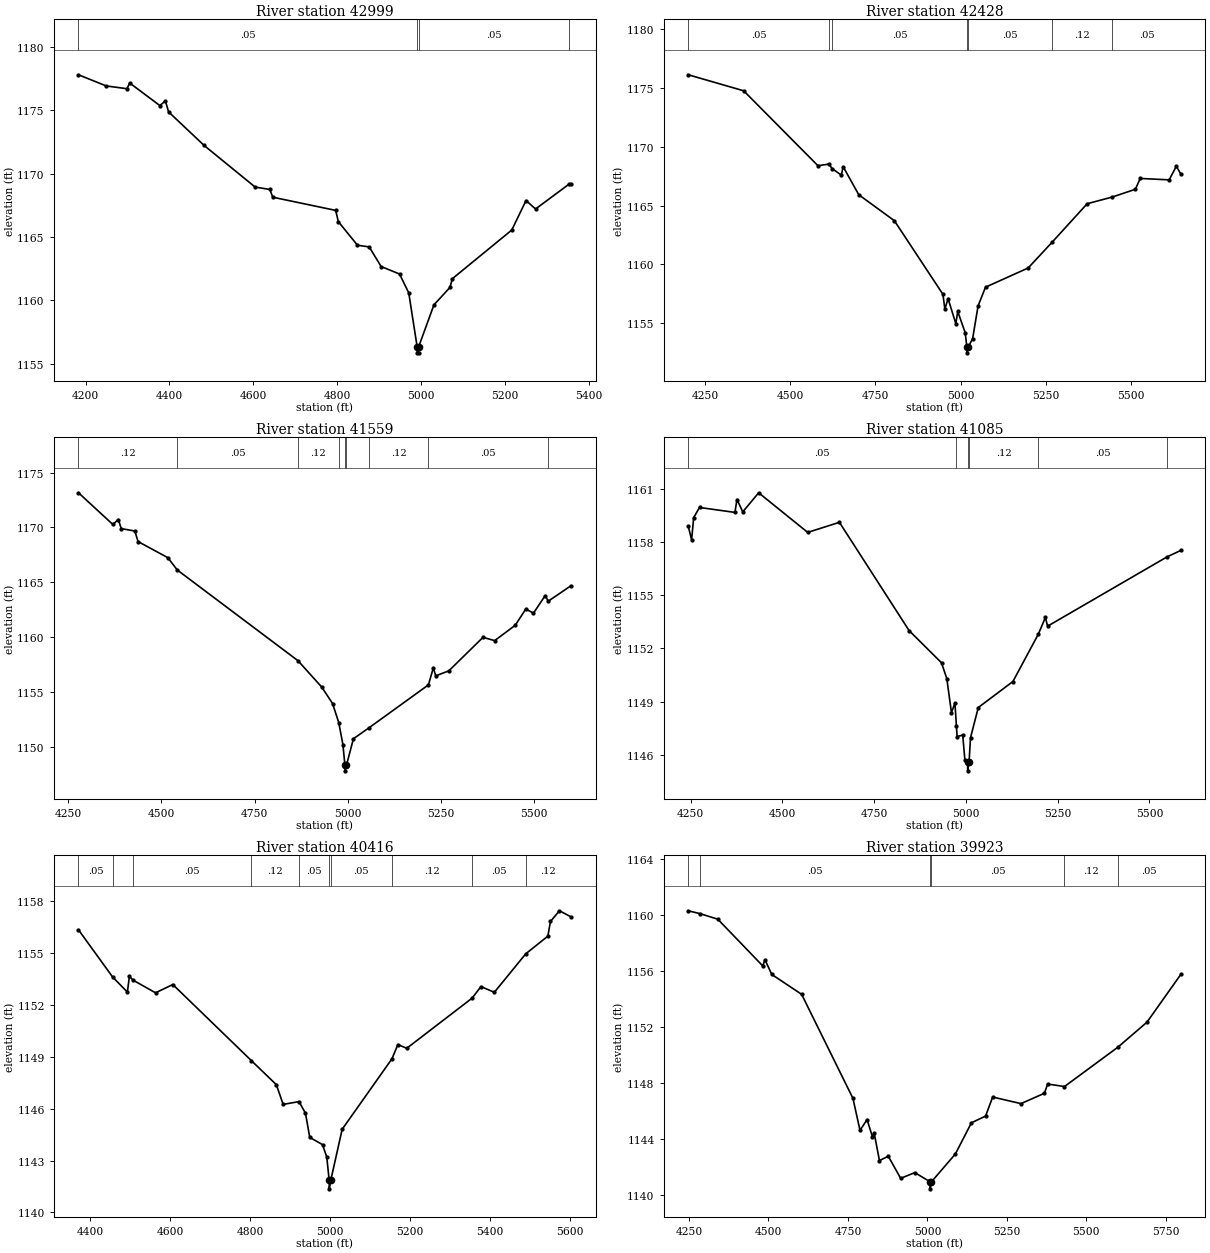
Type RM Length L Ch R = 1 ,42999   ,571,571,571
BEGIN DESCRIPTION:
Mapping XS 307592ac
END DESCRIPTION:
XS GIS Cut Line= 3
      2871625.78     10277075.05      2871209.12     10276554.22
      2870761.16     10276314.61
#Sta/Elev= 30
  4182.9 1177.79  4249.1 1176.91  4298.7 1176.69  4305.1 1177.14  4377.1 1175.36
  4390.3 1175.73  4397.9 1174.86  4482.8 1172.21  4604.4 1168.93  4639.6 1168.74
  4646.4 1168.13  4796.5 1167.09  4802.9  1166.2  4848.6 1164.34  4876.5 1164.21
    4905 1162.66  4948.9 1162.07  4970.9 1160.58  4990.8 1156.35    4991 1155.85
  4994.5 1155.85  4994.8 1156.35    5031 1159.64  5069.2 1161.01  5074.9  1161.7
  5216.7 1165.54  5250.7 1167.87  5273.4  1167.2  5352.9 1169.15  5357.9 1169.19
#Mann= 4 ,-1 , 0
  4182.9     .05       0  4990.8     .05       0  4994.8     .05       0
  5352.9     .12       0
Bank Sta=4990.8,4994.8
XS Rating Curve= 0 ,0
Exp/Cntr=0.3,0.1

Type RM Length L Ch R = 1 ,42428   ,869,869,869
BEGIN DESCRIPTION:
Mapping XS d3902596
END DESCRIPTION:
XS GIS Cut Line= 5
      2871860.18     10277007.36      2871729.95     10276892.76
      2871516.41     10276439.63      2871318.49     10276080.26
      2871069.57     10275820.97
#Sta/Elev= 30
  4201.3 1176.11  4363.6 1174.75  4581.5 1168.38  4613.4 1168.52  4623.1 1168.14
  4649.9 1167.58  4655.4  1168.3    4701 1165.92  4805.5 1163.71  4947.8 1157.46
  4953.6 1156.21  4963.1 1157.08  4985.7 1154.96  4991.4    1156  5013.2 1154.19
  5018.1 1152.98  5018.4 1152.48  5022.1 1152.98    5035 1153.68    5051 1156.47
  5072.8 1158.06  5197.8 1159.69  5267.8 1161.87  5370.8 1165.15  5444.3 1165.72
  5512.3 1166.38  5526.4  1167.3  5611.3 1167.18  5632.4 1168.34  5645.4 1167.67
#Mann= 7 ,-1 , 0
  4201.3     .05       0  4613.4     .12       0  4623.1     .05       0
  5018.1     .03       0  5022.1     .05       0  5267.8     .12       0
  5444.3     .05       0
Bank Sta=5018.1,5022.1
XS Rating Curve= 0 ,0
Exp/Cntr=0.3,0.1

Type RM Length L Ch R = 1 ,41559   ,474,474,474
BEGIN DESCRIPTION:
Mapping XS 38924565
END DESCRIPTION:
XS GIS Cut Line= 4
      2872209.11     10276444.83       2871948.7     10275944.84
      2871620.57     10275679.22      2871299.15      10275585.9
#Sta/Elev= 30
  4277.9 1173.15    4370 1170.26  4384.8 1170.71  4392.6 1169.88    4429 1169.66
  4437.7  1168.7  4517.4 1167.23    4543  1166.1  4866.5 1157.83  4930.5 1155.41
  4959.2 1153.92  4975.8 1152.19    4987 1150.17  4992.4 1148.28  4992.7 1147.78
  4996.4 1148.28  5015.2 1150.71  5056.7  1151.7  5216.2 1155.62  5229.4 1157.17
  5235.9 1156.45  5270.9  1156.9  5362.6 1159.96  5393.9 1159.66  5449.1 1161.06
  5477.2 1162.54    5498 1162.17  5529.2 1163.76  5537.7 1163.26  5598.5 1164.67
#Mann= 9 ,-1 , 0
  4277.9     .12       0    4543     .05       0  4866.5     .12       0
  4975.8     .05       0  4992.4     .05       0  4996.4     .05       0
  5056.7     .12       0  5216.2     .05       0  5537.7     .12       0
Bank Sta=4992.4,4996.4
XS Rating Curve= 0 ,0
Exp/Cntr=0.3,0.1

Type RM Length L Ch R = 1 ,41085   ,669,669,669
BEGIN DESCRIPTION:
Mapping XS 6eb853f8
END DESCRIPTION:
XS GIS Cut Line= 4
      2872485.16     10276095.89      2872203.91      10275606.3
      2871854.95     10275387.55      2871517.85     10275247.52
#Sta/Elev= 30
    4244  1158.9    4253 1158.14  4258.7  1159.4  4274.5 1159.97  4370.9 1159.69
  4376.6 1160.42  4392.4 1159.72  4435.6  1160.8  4569.3 1158.56  4655.6 1159.13
  4845.4 1153.01  4933.7 1151.19  4948.2 1150.29  4960.8 1148.37  4970.3 1148.91
  4974.3 1147.63  4976.2 1147.02  4991.5  1147.1  4997.4 1145.69  5004.8 1145.58
    5005 1145.08  5008.8 1145.58  5012.7 1146.95  5033.9 1148.66  5128.2 1150.13
  5197.8 1152.82  5216.6 1153.75  5222.8 1153.26  5548.4 1157.18  5585.5 1157.54
#Mann= 6 ,-1 , 0
    4244     .05       0  4974.3     .12       0  5004.8     .07       0
  5008.8     .12       0  5197.8     .05       0  5548.4     .12       0
Bank Sta=5004.8,5008.8
XS Rating Curve= 0 ,0
Exp/Cntr=0.3,0.1

Type RM Length L Ch R = 1 ,40416   ,493,493,493
BEGIN DESCRIPTION:
Mapping XS f799c593
END DESCRIPTION:
XS GIS Cut Line= 5
      2872474.75     10275814.67       2872448.7     10275580.26
       2872448.7     10275325.05      2872344.53     10275038.59
      2871953.86     10274845.86
#Sta/Elev= 30
  4371.2 1156.36  4456.4 1153.63  4493.5 1152.75  4498.5 1153.66  4507.9 1153.44
  4563.9 1152.71  4607.1 1153.19  4803.7 1148.78    4866 1147.39    4883 1146.25
  4922.6 1146.41  4938.8 1145.74  4949.5 1144.34  4981.4 1143.92    4992 1143.21
  4998.1 1141.86  4998.3 1141.36  5002.1 1141.86  5030.6 1144.81  5155.1 1148.89
  5169.8 1149.71  5192.2  1149.5  5355.4  1152.4  5377.7 1153.07  5411.1 1152.74
  5489.7 1154.97  5544.9 1155.99  5551.4 1156.84  5573.9 1157.46  5602.7 1157.11
#Mann= 10 ,-1 , 0
  4371.2     .05       0  4456.4     .12       0  4507.9     .05       0
  4803.7     .12       0  4922.6     .05       0  4998.1     .05       0
  5002.1     .05       0  5155.1     .12       0  5355.4     .05       0
  5489.7     .12       0
Bank Sta=4998.1,5002.1
XS Rating Curve= 0 ,0
Exp/Cntr=0.3,0.1

Type RM Length L Ch R = 1 ,39923   ,134,134,134
BEGIN DESCRIPTION:
Mapping XS e10e7dbe
END DESCRIPTION:
XS GIS Cut Line= 4
      2873407.04     10275392.76      2873172.66     10275147.97
      2872495.57     10274804.22        2872090.     10274606.63
#Sta/Elev= 30
  4247.7 1160.32  4285.3 1160.11  4340.4 1159.72  4481.9 1156.38  4488.9 1156.82
  4510.3 1155.77  4604.2 1154.35  4765.6 1146.92  4787.9 1144.63  4810.2  1145.4
  4826.8 1144.18  4832.4 1144.44  4849.1 1142.47  4876.9 1142.78  4915.8  1141.2
  4960.4 1141.61  5008.5 1140.95  5008.7 1140.45  5012.5 1140.95  5087.9 1142.94
  5138.4 1145.17    5183 1145.65  5205.2 1147.01  5294.3 1146.54  5368.1 1147.28
  5378.2 1147.94  5431.2 1147.76  5599.1 1150.57  5690.7 1152.36  5797.1 1155.77
#Mann= 6 ,-1 , 0
  4247.7     .12       0  4285.3     .05       0  5008.5     .03       0
  5012.5     .05       0  5431.2     .12       0  5599.1     .05       0
Bank Sta=5008.5,5012.5
XS Rating Curve= 0 ,0
Exp/Cntr=0.3,0.1

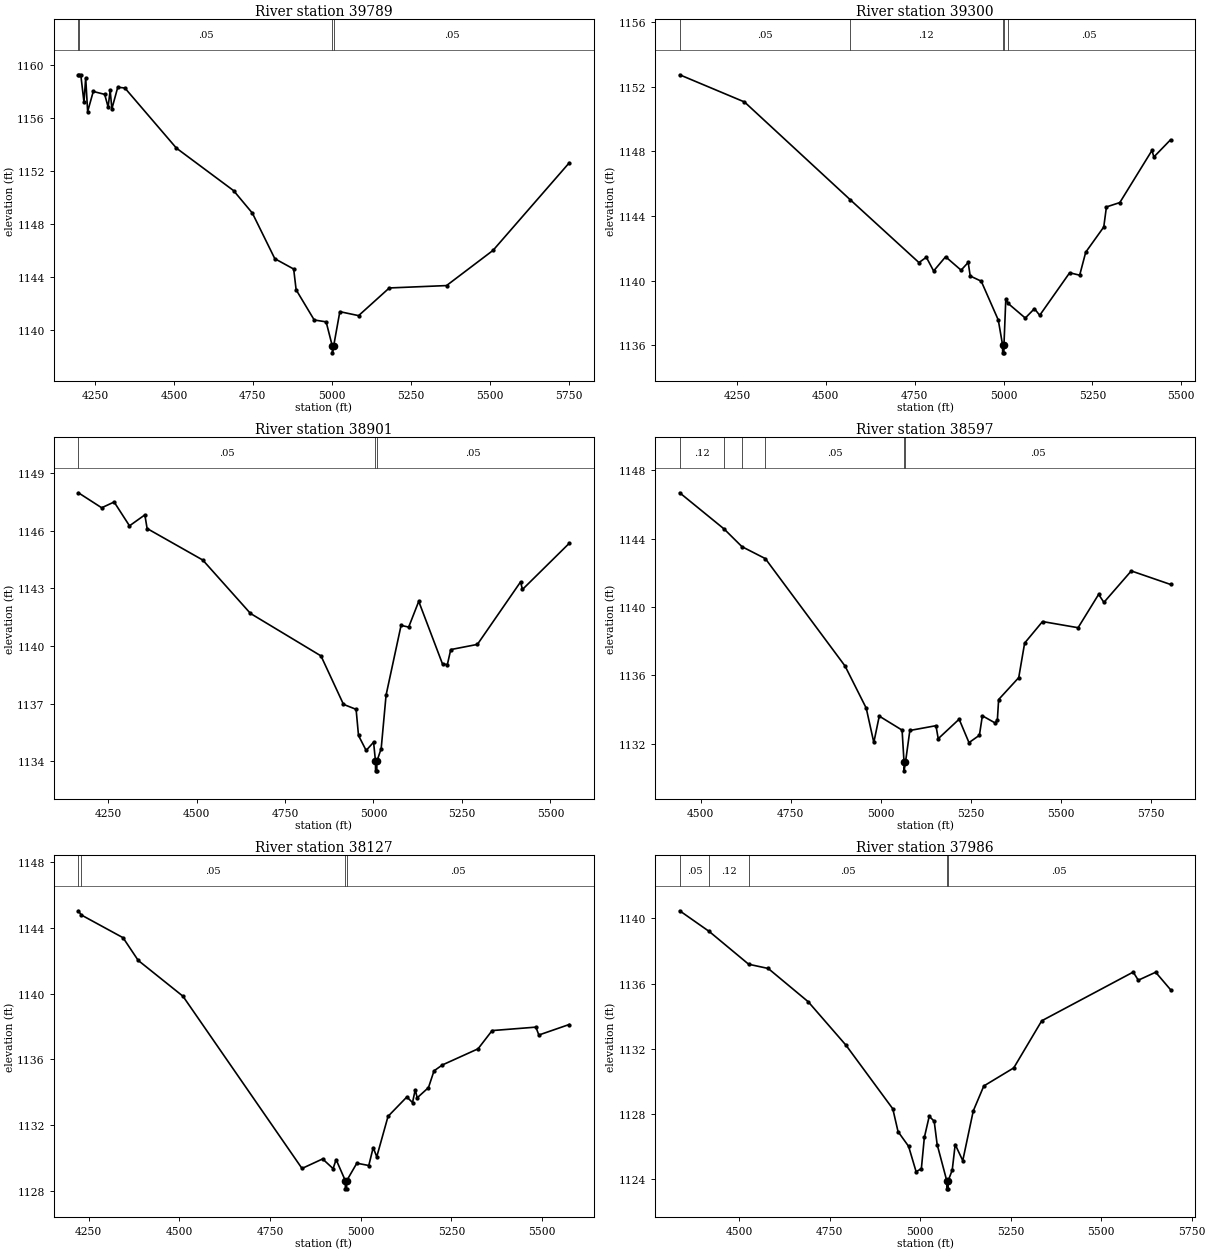
Type RM Length L Ch R = 1 ,39789   ,489,489,489
BEGIN DESCRIPTION:
Mapping XS acdb87ee
END DESCRIPTION:
XS GIS Cut Line= 6
       2873459.1     10275330.22      2873401.82     10275189.63
      2873209.12     10275033.38      2872964.32     10274897.97
      2872646.62     10274720.88      2872209.89     10274455.73
#Sta/Elev= 30
  4197.5 1159.26  4199.4 1159.25  4205.2 1159.23  4215.2 1157.18  4220.6 1159.04
  4226.8 1156.48  4244.6    1158  4280.8 1157.78  4291.6 1156.82  4298.1 1158.09
  4303.5 1156.69  4322.2 1158.32  4344.7 1158.26  4507.9 1153.72    4689 1150.51
  4748.5 1148.81  4819.5 1145.37  4879.2 1144.59    4887 1143.02  4944.3 1140.74
    4982  1140.6  5001.7 1138.76  5001.9 1138.26  5005.7 1138.76  5025.4 1141.37
  5084.8 1141.07    5182 1143.16  5363.3 1143.34  5510.6    1146  5751.8 1152.61
#Mann= 4 ,-1 , 0
  4197.5     .12       0  4199.4     .05       0  5001.7     .03       0
  5005.7     .05       0
Bank Sta=5001.7,5005.7
XS Rating Curve= 0 ,0
Exp/Cntr=0.3,0.1

Type RM Length L Ch R = 1 ,39300   ,399,399,399
BEGIN DESCRIPTION:
Mapping XS b2ef1210
END DESCRIPTION:
XS GIS Cut Line= 4
      2873490.35     10275033.37      2872922.66     10274590.67
      2872625.78     10274486.51      2872313.29     10274335.47
#Sta/Elev= 30
  4088.5 1152.73  4270.8 1151.05  4568.8    1145    4762 1141.12  4782.8 1141.45
  4803.3  1140.6    4837 1141.48  4880.6 1140.65  4900.6 1141.13  4906.3 1140.29
  4937.3 1139.97  4985.3 1137.57  4997.3 1136.04  4997.6 1135.54  5001.1 1135.54
  5001.3 1136.04  5006.5 1138.88  5012.7  1138.6  5061.3 1137.69    5087 1138.27
  5101.9 1137.86  5186.2 1140.49  5214.4 1140.34  5231.4 1141.76  5282.2 1143.32
  5289.7 1144.56  5327.4 1144.83  5417.8 1148.05  5423.3 1147.65  5470.1 1148.71
#Mann= 5 ,-1 , 0
  4088.5     .05       0  4568.8     .12       0  4997.3     .07       0
  5001.3     .12       0  5012.7     .05       0
Bank Sta=4997.3,5001.3
XS Rating Curve= 0 ,0
Exp/Cntr=0.3,0.1

Type RM Length L Ch R = 1 ,38901   ,304,304,304
BEGIN DESCRIPTION:
Mapping XS 638d2cf0
END DESCRIPTION:
XS GIS Cut Line= 4
      2873604.94     10274866.71      2873104.95     10274476.09
      2872865.37     10274215.67      2872500.77     10274054.21
#Sta/Elev= 30
  4166.1 1147.97  4231.9 1147.19  4267.1 1147.49  4310.5 1146.25  4353.9 1146.82
  4360.3 1146.11  4517.6 1144.47  4652.4 1141.69  4851.7 1139.48  4915.2 1136.96
  4950.9  1136.7  4957.7 1135.34  4979.3 1134.56  5000.3 1134.99  5005.7    1134
  5005.9  1133.5  5009.4  1133.5  5009.7    1134  5021.8 1134.66  5035.6 1137.44
    5078 1141.07  5099.5 1140.98  5127.9 1142.32  5195.1 1139.06  5208.8 1139.03
  5218.4 1139.81  5293.7 1140.08  5415.6 1143.33  5421.1 1142.94  5553.2 1145.34
#Mann= 3 ,-1 , 0
  4166.1     .05       0  5005.7     .03       0  5009.7     .05       0
Bank Sta=5005.7,5009.7
XS Rating Curve= 0 ,0
Exp/Cntr=0.3,0.1

Type RM Length L Ch R = 1 ,38597   ,470,470,470
BEGIN DESCRIPTION:
Mapping XS fb81add2
END DESCRIPTION:
XS GIS Cut Line= 4
       2873719.5     10274543.78      2873193.49     10274200.05
      2872990.37      10274043.8      2872569.61     10273820.43
#Sta/Elev= 30
  4442.2 1146.68    4565 1144.57  4614.8 1143.53  4679.7 1142.83  4900.7 1136.55
  4959.4 1134.09  4980.5 1132.08  4995.6 1133.62  5058.9  1132.8  5064.3 1130.92
  5064.5 1130.42  5068.3 1130.92  5080.4 1132.78  5152.8 1133.06  5159.1  1132.3
  5217.1 1133.44  5244.4 1132.07  5273.3  1132.5  5281.5 1133.64  5316.8 1133.22
  5323.1  1133.4  5326.6 1134.59  5382.3 1135.87  5398.7 1137.89  5448.3 1139.15
  5546.9 1138.79  5603.9 1140.74  5618.5 1140.27  5694.4 1142.11  5803.2 1141.32
#Mann= 6 ,-1 , 0
  4442.2     .12       0    4565     .05       0  4614.8     .12       0
  4679.7     .05       0  5064.3     .05       0  5068.3     .05       0
Bank Sta=5064.3,5068.3
XS Rating Curve= 0 ,0
Exp/Cntr=0.3,0.1

Type RM Length L Ch R = 1 ,38127   ,141,141,141
BEGIN DESCRIPTION:
Mapping XS 4065e770
END DESCRIPTION:
XS GIS Cut Line= 3
      2873728.07     10274332.35      2873139.56     10273900.09
      2872571.88     10273644.89
#Sta/Elev= 30
  4222.1 1145.04  4229.7 1144.79  4345.2  1143.4  4386.9 1142.02  4510.3 1139.84
  4838.3 1129.36  4895.1 1129.94    4924 1129.35  4932.3  1129.9  4957.6 1128.62
  4957.8 1128.12  4961.3 1128.12  4961.6 1128.62  4989.4 1129.68  5022.3 1129.54
  5034.5 1130.63  5044.3 1130.07  5075.4 1132.53  5127.2 1133.71  5142.9 1133.37
  5150.3 1134.15  5155.8 1133.66  5186.8 1134.28  5202.1  1135.3  5225.3 1135.66
  5323.4 1136.64  5362.2 1137.75  5482.8 1137.96    5491 1137.48  5574.7 1138.12
#Mann= 4 ,-1 , 0
  4222.1     .12       0  4229.7     .05       0  4957.6     .03       0
  4961.6     .05       0
Bank Sta=4957.6,4961.6
XS Rating Curve= 0 ,0
Exp/Cntr=0.3,0.1

Type RM Length L Ch R = 1 ,37986   ,413,413,413
BEGIN DESCRIPTION:
Mapping XS ca10fb9b
END DESCRIPTION:
XS GIS Cut Line= 4
      2873802.88      10274163.6       2873323.7     10273913.59
      2873078.91     10273726.09      2872610.39     10273533.48
#Sta/Elev= 30
  4336.2 1140.47  4417.8  1139.2  4526.7 1137.19  4580.7 1136.93  4691.1 1134.89
  4795.5 1132.22  4924.7 1128.32  4939.2 1126.92  4968.3 1126.02  4989.1 1124.46
  5003.6 1124.65  5011.8 1126.56  5025.3 1127.86    5039 1127.56  5047.2 1126.13
  5073.7 1123.91    5074 1123.41  5077.5 1123.41  5077.7 1123.91  5088.8 1124.56
    5097 1126.13  5117.9 1125.14  5146.9 1128.19    5176 1129.72  5258.7 1130.83
    5336 1133.72  5588.6 1136.71  5602.6 1136.21  5650.6  1136.7  5691.6 1135.63
#Mann= 5 ,-1 , 0
  4336.2     .05       0  4417.8     .12       0  4526.7     .05       0
  5073.7     .03       0  5077.7     .05       0
#XS Ineff= 2 , 0
       0    5025  1127.8               0
Permanent Ineff=
       F       F
Bank Sta=5073.7,5077.7
XS Rating Curve= 0 ,0
Exp/Cntr=0.3,0.1

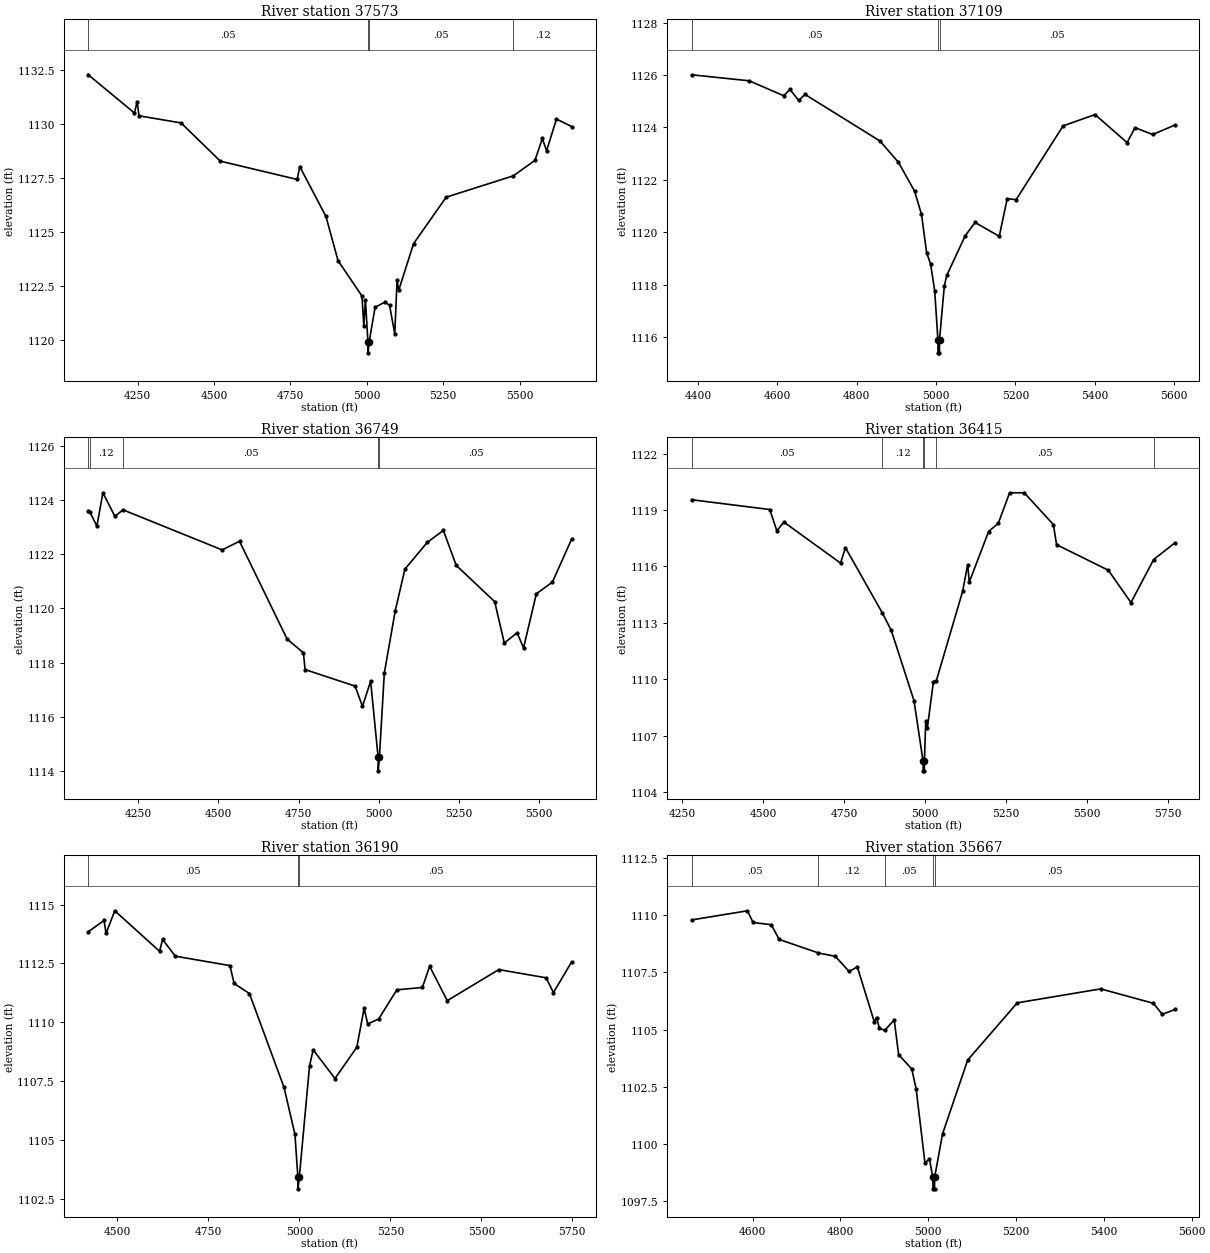
Type RM Length L Ch R = 1 ,37573   ,464,464,464
BEGIN DESCRIPTION:
Mapping XS 41ace97d
END DESCRIPTION:
XS GIS Cut Line= 4
      2874110.17     10273950.06       2873636.2     10273627.13
      2873193.49     10273455.26       2872699.7     10273252.54
#Sta/Elev= 30
  4088.4 1132.28  4239.5 1130.51  4248.4 1131.04  4254.4 1130.38    4392 1130.05
  4520.7 1128.28  4772.4 1127.43  4780.5 1128.03  4866.3 1125.72  4905.9 1123.67
  4984.3 1122.03  4990.2 1120.65  4995.6 1121.86  5003.7  1119.9    5004  1119.4
  5007.7  1119.9  5027.2 1121.51  5059.4 1121.75  5074.6  1121.6  5091.6 1120.28
  5099.1 1122.76  5104.5  1122.3  5153.2 1124.46  5259.9 1126.61    5480  1127.6
  5550.6 1128.32  5574.6 1129.33  5588.5 1128.76  5620.9 1130.23  5670.6 1129.88
#Mann= 4 ,-1 , 0
  4088.4     .05       0  5003.7     .03       0  5007.7     .05       0
    5480     .12       0
Bank Sta=5003.7,5007.7
XS Rating Curve= 0 ,0
Exp/Cntr=0.3,0.1

Type RM Length L Ch R = 1 ,37109   ,360,360,360
BEGIN DESCRIPTION:
Mapping XS f3284dca
END DESCRIPTION:
XS GIS Cut Line= 4
      2874157.07     10273418.82      2873828.91     10273236.51
      2873443.49     10273163.59      2872995.56     10273111.51
#Sta/Elev= 30
  4383.7 1126.01  4528.8 1125.78  4615.7 1125.21  4631.7 1125.45  4653.5 1125.03
  4669.5 1125.26  4858.6 1123.48  4904.9 1122.67  4945.6 1121.57  4963.2 1120.68
  4976.1 1119.22  4986.3 1118.77  4996.5 1117.76  5004.6 1115.89  5004.9 1115.39
  5008.4 1115.39  5008.6 1115.89  5020.7 1117.94    5027 1118.35    5073 1119.85
  5098.2 1120.37  5159.2 1119.84  5179.3 1121.28  5201.7 1121.24  5320.3 1124.06
  5400.8 1124.49  5481.4 1123.42  5501.5 1123.99    5546 1123.73  5602.3 1124.09
#Mann= 3 ,-1 , 0
  4383.7     .05       0  5004.6     .03       0  5008.6     .05       0
Bank Sta=5004.6,5008.6
XS Rating Curve= 0 ,0
Exp/Cntr=0.3,0.1

Type RM Length L Ch R = 1 ,36749   ,334,334,334
BEGIN DESCRIPTION:
Mapping XS b1ca3f1e
END DESCRIPTION:
XS GIS Cut Line= 3
      2874368.73     10273176.13      2873498.94     10272863.63
      2872915.59     10272858.42
#Sta/Elev= 30
  4094.2 1123.58  4099.1 1123.56    4121 1123.04  4139.9 1124.27  4177.1  1123.4
  4202.5 1123.64  4511.8 1122.16  4565.9 1122.48  4714.2 1118.87  4765.1 1118.36
  4770.4 1117.74  4926.3 1117.13  4949.4 1116.38  4974.8 1117.31  4998.2  1114.5
  4998.5    1114  5002.2  1114.5  5017.5 1117.61  5051.7 1119.92  5081.7 1121.45
  5151.7 1122.44  5201.7 1122.88  5241.7 1121.59  5361.7 1120.25  5391.7 1118.72
  5431.7  1119.1  5451.7 1118.54  5491.7 1120.54  5541.7 1120.97  5601.8 1122.56
#Mann= 5 ,-1 , 0
  4094.2     .05       0  4099.1     .12       0  4202.5     .05       0
  4998.2     .05       0  5002.2     .05       0
Bank Sta=4998.2,5002.2
XS Rating Curve= 0 ,0
Exp/Cntr=0.3,0.1

Type RM Length L Ch R = 1 ,36415   ,225,225,225
BEGIN DESCRIPTION:
Mapping XS d621f59c
END DESCRIPTION:
XS GIS Cut Line= 4
      2874386.24     10272861.52      2873896.62     10272642.76
      2873427.87      10272606.3       2872939.5      10272606.3
#Sta/Elev= 30
  4278.4 1119.55    4520 1119.03  4541.9  1117.9  4563.8 1118.36    4739 1116.18
    4754    1117  4868.1 1113.53  4895.8  1112.6  4966.1 1108.86  4994.2 1105.63
  4994.4 1105.13  4997.9 1105.13  4998.2 1105.63  5002.4 1107.77  5007.4 1107.42
  5026.2 1109.88  5034.9 1109.91  5116.5 1114.68    5132  1116.1    5137 1115.17
  5196.8 1117.86  5226.8  1118.3  5261.7 1119.92    5307 1119.92    5397 1118.23
    5407 1117.16    5567  1115.8    5637 1114.08  5707.1 1116.37  5773.2 1117.26
#Mann= 6 ,-1 , 0
  4278.4     .05       0  4868.1     .12       0  4994.2     .07       0
  4998.2     .12       0  5034.9     .05       0  5707.1     .12       0
Bank Sta=4994.2,4998.2
XS Rating Curve= 0 ,0
Exp/Cntr=0.3,0.1

Type RM Length L Ch R = 1 ,36190   ,523,523,523
BEGIN DESCRIPTION:
Mapping XS baf901b2
END DESCRIPTION:
XS GIS Cut Line= 4
       2874287.2     10272595.87       2873823.7     10272408.38
      2873490.37     10272403.17      2872995.57      10272418.8
#Sta/Elev= 30
  4419.7 1113.85  4463.1 1114.33  4468.5 1113.78  4492.6 1114.74  4615.5 1113.02
    4624 1113.52  4658.9 1112.81    4809 1112.41  4820.5 1111.65  4862.6 1111.22
  4957.7 1107.23  4987.7 1105.23  4995.7 1103.42    4996 1102.92  4999.7 1103.42
  5027.7 1108.14  5037.7 1108.83  5097.7 1107.61  5157.7 1108.94  5177.7 1110.59
  5187.7 1109.93  5217.7 1110.14  5267.7 1111.38  5337.8 1111.48  5357.8 1112.38
  5406.2 1110.92  5547.9 1112.24    5678 1111.89    5698 1111.26  5748.1 1112.57
#Mann= 3 ,-1 , 0
  4419.7     .05       0  4995.7     .05       0  4999.7     .05       0
Bank Sta=4995.7,4999.7
XS Rating Curve= 0 ,0
Exp/Cntr=0.3,0.1

Type RM Length L Ch R = 1 ,35667   ,411,411,411
BEGIN DESCRIPTION:
Mapping XS 9e1618a8
END DESCRIPTION:
XS GIS Cut Line= 4
      2873979.97     10272184.43      2873568.49     10272064.63
      2873245.57     10272054.22      2872896.58     10272064.63
#Sta/Elev= 30
  4461.3 1109.79  4588.4 1110.19  4601.2 1109.68  4642.8 1109.58  4660.6 1108.94
  4749.8 1108.35  4788.6  1108.2  4819.9 1107.54  4838.6 1107.74  4877.3 1105.34
  4882.5 1105.53  4888.7 1105.07  4900.8 1104.97  4922.7 1105.42  4932.7 1103.91
  4962.7 1103.28  4972.7  1102.4  4992.7 1099.17  5002.7 1099.36  5010.7 1098.55
    5011 1098.05  5014.5 1098.05  5014.7 1098.55  5032.7 1100.45  5089.9 1103.67
  5202.8 1106.17  5392.9 1106.78    5513 1106.15    5533 1105.67  5562.1 1105.88
#Mann= 5 ,-1 , 0
  4461.3     .05       0  4749.8     .12       0  4900.8     .05       0
  5010.7     .05       0  5014.7     .05       0
Bank Sta=5010.7,5014.7
XS Rating Curve= 0 ,0
Exp/Cntr=0.3,0.1

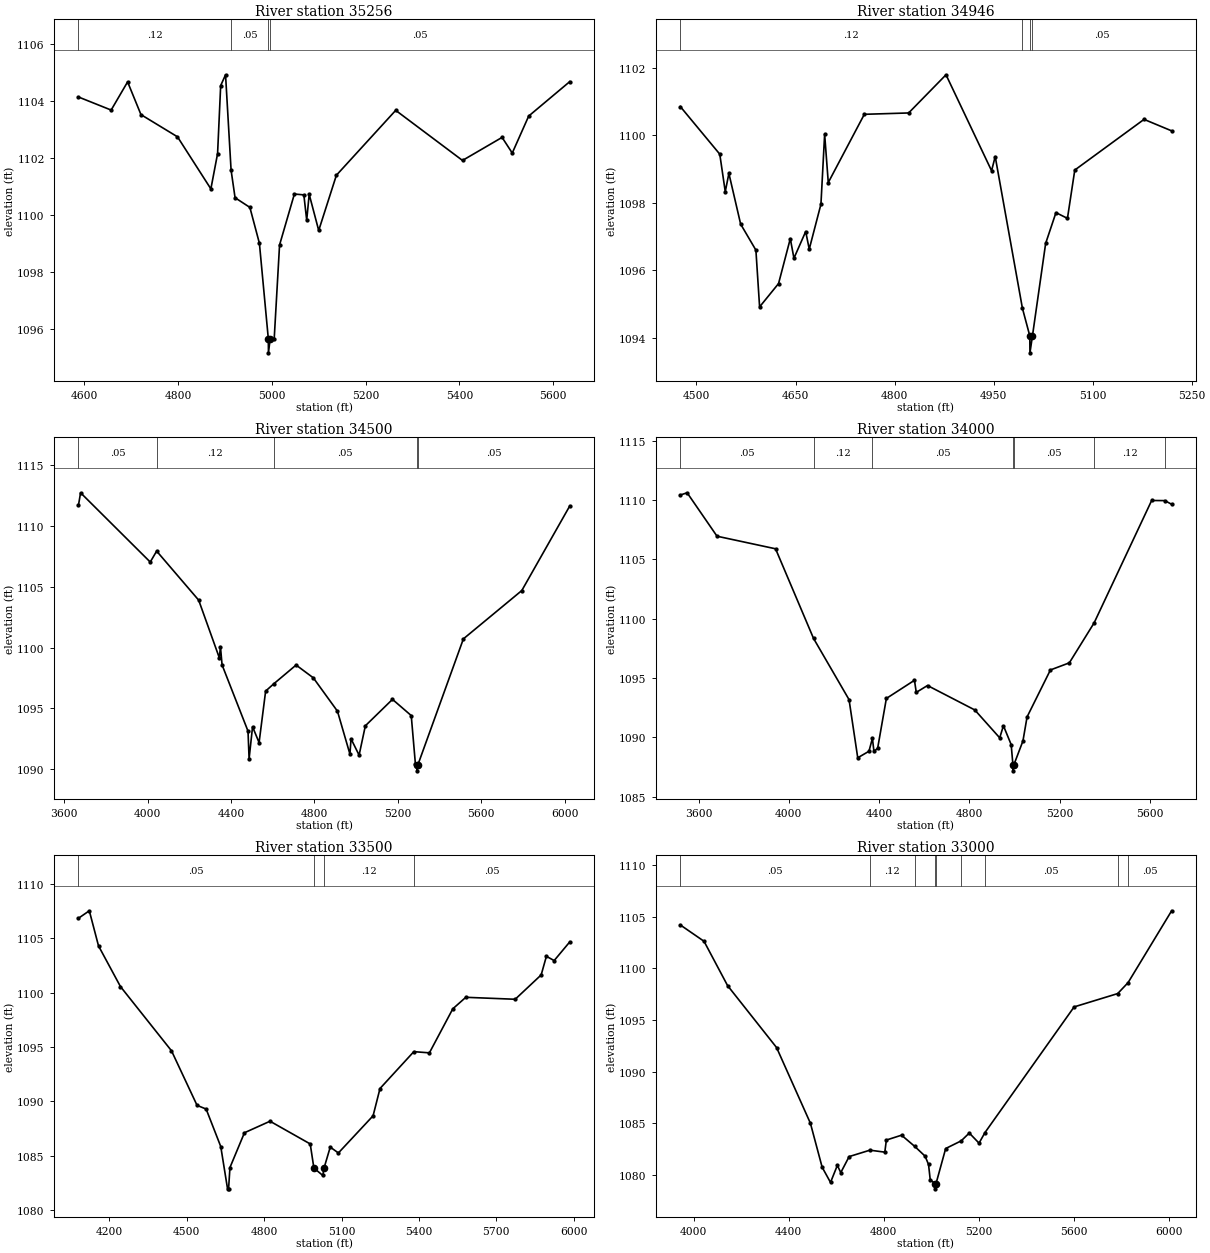
Type RM Length L Ch R = 1 ,35256   ,310,310,310
BEGIN DESCRIPTION:
Mapping XS 70e0dbe5
END DESCRIPTION:
XS GIS Cut Line= 4
        2873782.     10271825.02      2873547.66     10271621.92
      2873125.78     10271762.55      2872908.36     10271959.26
#Sta/Elev= 30
  4587.4 1104.14  4657.2 1103.68  4692.3 1104.67  4720.8 1103.52  4798.7 1102.74
  4869.9 1100.91  4884.2 1102.15  4890.8 1104.54  4901.2 1104.92    4913 1101.57
  4921.5  1100.6  4953.1 1100.26  4973.4    1099  4992.4 1095.65  4992.7 1095.15
  4996.4 1095.65    5005 1095.65  5016.4 1098.94    5048 1100.73  5068.2  1100.7
  5074.3 1099.81  5079.6 1100.72  5099.9 1099.45  5137.6 1101.39  5264.1 1103.67
  5406.6 1101.91    5491 1102.72  5512.7 1102.17  5547.8 1103.47  5635.4 1104.68
#Mann= 4 ,-1 , 0
  4587.4     .12       0    4913     .05       0  4992.4     .05       0
  4996.4     .05       0
#XS Ineff= 2 , 0
       0    4895                       0
Permanent Ineff=
       F       F
Bank Sta=4992.4,4996.4
XS Rating Curve= 0 ,0
Exp/Cntr=0.3,0.1

Type RM Length L Ch R = 1 ,34946   ,446,446,446
BEGIN DESCRIPTION:
Mapping XS 29e1cf43
END DESCRIPTION:
XS GIS Cut Line= 4
      2873740.36     10271496.92      2873412.24     10271351.09
      2873162.24     10271465.672873072.5536244410271529.3983456
#Sta/Elev= 30
  4475.5 1100.85  4535.3 1099.44  4543.6 1098.33  4549.1 1098.87  4566.9 1097.37
    4590  1096.6  4595.6 1094.92  4624.3 1095.61  4642.1 1096.94  4647.6 1096.36
  4665.4 1097.15  4670.8 1096.63  4688.5 1097.96  4694.1 1100.03  4699.6  1098.6
  4754.2 1100.62  4821.3 1100.66  4877.9 1101.79  4946.9 1098.95  4952.4 1099.37
  4993.6 1094.88  5004.8 1094.06    5005 1093.56  5008.8 1094.06  5028.8  1096.8
  5044.4 1097.71  5061.8 1097.54  5072.9 1098.97  5177.8 1100.47  5219.6 1100.13
#Mann= 4 ,-1 , 0
  4475.5     .12       0  4993.6     .05       0  5004.8     .03       0
  5008.8     .05       0
#XS Ineff= 2 , 0
       0  4877.9                       0
Permanent Ineff=
       F       F
Bank Sta=5004.8,5008.8
XS Rating Curve= 0 ,0
Exp/Cntr=0.3,0.1

Type RM Length L Ch R = 1 ,34500   ,500,500,500
BEGIN DESCRIPTION:
RED ROCK CREEK 69.0
END DESCRIPTION:
XS GIS Cut Line= 3
      2874505.66     10271453.11      2873229.85     10271070.31
      2872205.68     10271103.11
#Sta/Elev= 30
    3668 1111.67  3678.4 1112.71  4012.5 1107.02  4043.2 1107.92  4244.8 1103.89
  4343.9 1099.15  4349.2 1100.07    4357 1098.57  4481.4 1093.13  4486.6 1090.86
  4503.2 1093.49  4534.5 1092.19  4565.9 1096.42  4603.7    1097    4712 1098.56
  4794.6 1097.51  4910.4 1094.77  4970.3 1091.24  4975.5  1092.5  5014.2 1091.16
  5044.2 1093.57  5174.3 1095.74  5264.3 1094.41  5284.3 1090.42  5292.3 1090.37
  5292.6 1089.87  5296.3 1090.37  5514.4 1100.71  5794.6 1104.68  6024.7 1111.63
#Mann= 5 ,-1 , 0
    3668     .05       0  4043.2     .12       0  4603.7     .05       0
  5292.3     .03       0  5296.3     .05       0
#XS Ineff= 2 , 0
       0    5144                       0
Permanent Ineff=
       F       F
Bank Sta=5292.3,5296.3
XS Rating Curve= 0 ,0
Exp/Cntr=0.3,0.1

Type RM Length L Ch R = 1 ,34000   ,500,500,500
BEGIN DESCRIPTION:
RED ROCK CREEK 68.0
END DESCRIPTION:
XS GIS Cut Line= 3
      2874405.69     10271303.11       2873092.6     10270617.74
       2872405.7     10270503.11
#Sta/Elev= 30
  3518.8 1110.43  3549.1 1110.62  3681.6 1106.96    3941  1105.9  4109.3 1098.35
  4266.7 1093.19  4305.2 1088.29    4355 1088.84  4370.2 1089.93  4377.1 1088.82
  4393.5  1089.1  4432.1 1093.29  4556.6 1094.82  4564.6  1093.8  4614.4 1094.38
    4824 1092.32  4934.4 1089.97  4950.9 1090.99  4985.2  1089.4    4993 1087.69
  4993.3 1087.19    4997 1087.69  5037.4 1089.71  5055.6 1091.73  5159.1 1095.69
    5243 1096.29  5352.9 1099.66  5607.8 1109.97    5666 1109.96  5696.4 1109.65
#Mann= 7 ,-1 , 0
  3518.8     .05       0  4109.3     .12       0  4370.2     .05       0
    4993     .03       0    4997     .05       0  5352.9     .12       0
    5666     .05       0
#XS Ineff= 2 , 0
       0    4824                       0
Permanent Ineff=
       F       F
Bank Sta=4993,4997
XS Rating Curve= 0 ,0
Exp/Cntr=0.3,0.1

Type RM Length L Ch R = 1 ,33500   ,500,500,500
BEGIN DESCRIPTION:
RED ROCK CREEK 67.0
END DESCRIPTION:
XS GIS Cut Line= 3
      2874155.66     10270953.09      2873482.65     10270325.52
      2872505.69     10270203.11
#Sta/Elev= 30
  4079.8 1106.84    4122 1107.53  4157.7  1104.3  4242.7 1100.56  4440.6 1094.65
  4539.7 1089.63  4574.9 1089.29  4631.6 1085.84  4657.9 1081.95  4661.9 1081.95
  4667.2 1083.91  4723.4 1087.11  4822.6 1088.17  4978.4 1086.08  4992.6 1083.86
  5027.2 1083.18  5031.7 1083.84    5056 1085.79  5087.6 1085.25  5222.1 1088.67
  5248.9 1091.18    5380 1094.57  5440.4 1094.46  5531.1 1098.51  5581.5 1099.57
    5773 1099.39  5873.7 1101.63  5893.9 1103.34  5924.1 1102.95  5984.6 1104.67
#Mann= 4 ,-1 , 0
  4079.8     .05       0  4992.6     .05       0  5031.7     .12       0
    5380     .05       0
#XS Ineff= 2 , 0
       0 4820.93                       0
Permanent Ineff=
       F       F
Bank Sta=4992.6,5031.7
XS Rating Curve= 0 ,0
Exp/Cntr=0.3,0.1

Type RM Length L Ch R = 1 ,33000   ,500,500,500
BEGIN DESCRIPTION:
RED ROCK CREEK 66.0
END DESCRIPTION:
XS GIS Cut Line= 3
      2874305.68     10270703.11      2873641.63     10269881.38
      2872655.71     10269653.12
#Sta/Elev= 30
  3943.5 1104.19  4043.4 1102.61  4142.6 1098.32  4348.8 1092.33  4491.2 1085.01
  4540.7 1080.75  4575.9 1079.28  4604.7 1080.93  4619.1 1080.23  4654.3 1081.78
  4741.7  1082.4  4804.5 1082.21    4811 1083.38  4874.9 1083.85  4930.7 1082.76
  4974.1 1081.82  4988.5 1081.02  4995.7 1079.54    5016 1079.16  5016.2 1078.66
    5020 1079.16  5060.7 1082.56  5125.9  1083.3  5160.1 1084.06  5201.1 1083.08
  5226.3 1084.11  5601.4 1096.26  5784.9 1097.55  5828.6 1098.61    6012 1105.56
#Mann= 9 ,-1 , 0
  3943.5     .05       0  4741.7     .12       0  4930.7     .05       0
    5016     .05       0    5020     .05       0  5125.9     .12       0
  5226.3     .05       0  5784.9     .12       0  5828.6     .05       0
#XS Ineff= 2 , 0
       0  4874.9                       0
Permanent Ineff=
       F       F
Bank Sta=5016,5020
XS Rating Curve= 0 ,0
Exp/Cntr=0.3,0.1