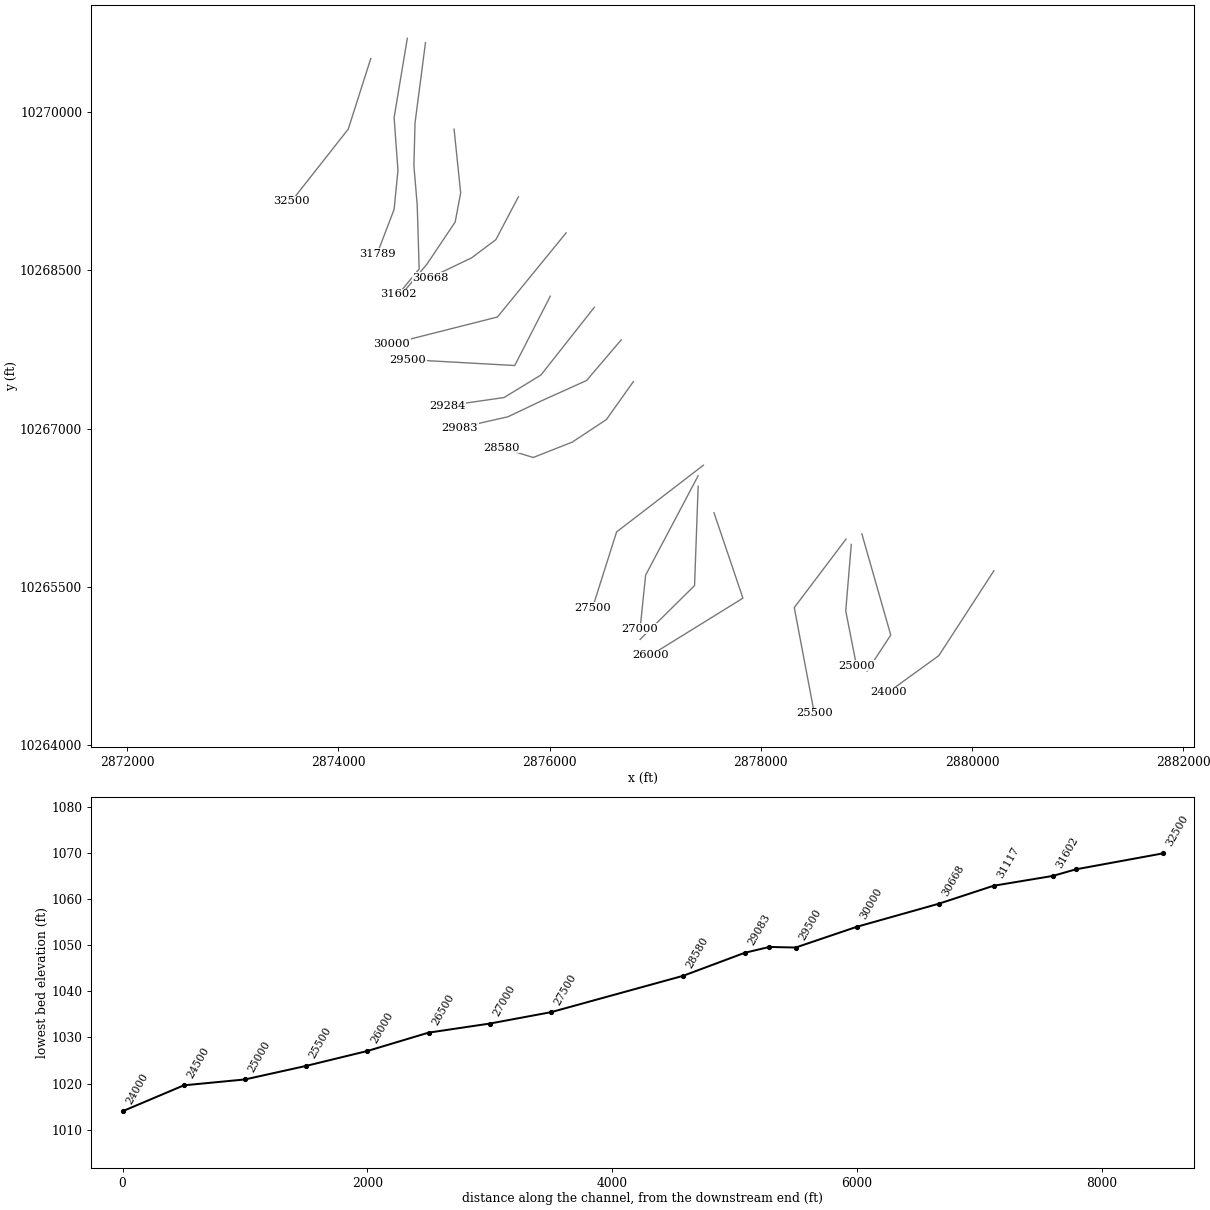
HEC-RAS study RED ROCK CREEK.prj: RED ROCK CREEK Base Level Engineering

--- RED ROCK CREEK.g01 (geometry) --- (continued)

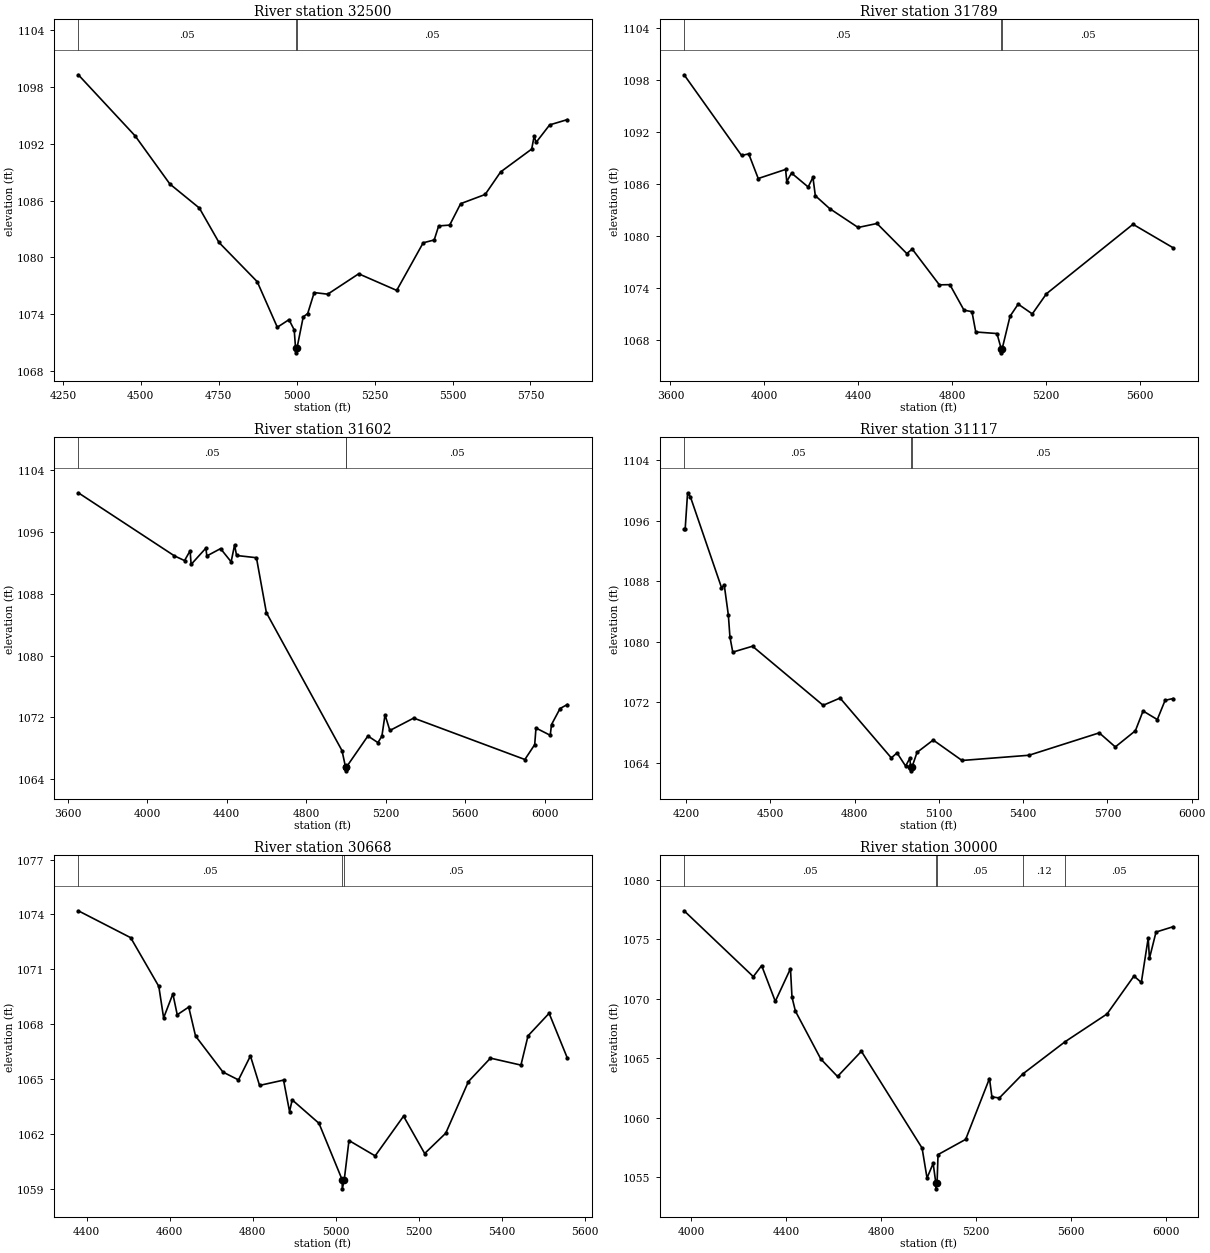
Type RM Length L Ch R = 1 ,32500   ,711,711,711
BEGIN DESCRIPTION:
RED ROCK CREEK 65.0
END DESCRIPTION:
XS GIS Cut Line= 3
      2874305.68     10270503.11      2874092.82     10269835.52
      2873555.71     10269153.15
#Sta/Elev= 30
  4299.3 1099.28  4481.7 1092.83  4593.2 1087.75  4687.6 1085.22  4750.6 1081.59
  4873.3 1077.45  4937.8 1072.64  4975.2 1073.44    4992 1072.36  4996.3 1070.44
  4996.7 1069.94  5000.9 1070.44  5020.9 1073.73  5035.3 1074.09  5056.1  1076.3
  5099.5 1076.13  5198.9 1078.28  5320.8 1076.53  5405.8 1081.55  5441.1 1081.85
  5455.5 1083.33  5490.8 1083.42    5526 1085.68  5604.6 1086.65  5654.3 1089.03
  5753.9 1091.44  5761.8  1092.8  5768.2 1092.15  5811.5 1093.99  5868.4 1094.55
#Mann= 3 ,-1 , 0
  4299.3     .05       0  4996.3     .05       0  5000.9     .05       0
Bank Sta=4996.3,5000.9
XS Rating Curve= 0 ,0
Exp/Cntr=0.3,0.1

Type RM Length L Ch R = 1 ,31789   ,187,187,187
BEGIN DESCRIPTION:
Mapping XS 554084d3
END DESCRIPTION:
XS GIS Cut Line= 5
      2874651.82      10270694.8      2874526.82     10269944.84
      2874563.28     10269444.84      2874526.82     10269075.05
      2874365.38      10268653.2
#Sta/Elev= 30
  3658.2 1098.62  3903.2 1089.29  3933.6 1089.48  3974.2 1086.63  4090.8 1087.68
  4095.9 1086.28  4116.1 1087.26  4187.1 1085.65  4207.4 1086.77  4217.6 1084.64
  4278.4 1083.16    4400 1080.97  4480.4 1081.43  4607.4 1077.96  4630.8 1078.47
  4746.3 1074.34  4791.2 1074.36  4851.4 1071.41  4885.3 1071.24  4901.5 1068.89
  4991.9 1068.71  5009.7 1066.98    5010 1066.48  5014.4 1066.98  5047.7 1070.71
  5082.3 1072.11  5142.6 1070.98  5202.9 1073.31  5571.9 1081.34  5743.1 1078.62
#Mann= 3 ,-1 , 0
  3658.2     .05       0  5009.7     .03       0  5014.4     .05       0
Bank Sta=5009.7,5014.4
XS Rating Curve= 0 ,0
Exp/Cntr=0.3,0.1

Type RM Length L Ch R = 1 ,31602   ,485,485,485
BEGIN DESCRIPTION:
Mapping XS 12b3d8da
END DESCRIPTION:
XS GIS Cut Line= 6
       2874823.7     10270653.19      2874724.74     10269892.76
      2874714.32     10269486.51      2874745.57     10269116.72
      2874764.06     10268510.73      2874566.13     10268271.12
#Sta/Elev= 30
  3652.6 1101.11  4136.3 1092.93  4187.2 1092.32  4215.4 1093.59  4220.4 1091.82
  4294.5 1093.93  4299.5 1092.92  4368.5 1093.87  4421.8 1092.16  4439.1 1094.35
  4449.1 1092.98  4549.1 1092.69  4599.2 1085.56  4979.8 1067.68  4997.4 1065.56
  4997.8 1065.06  5002.2 1065.56  5110.2 1069.58  5160.4 1068.72  5180.5 1069.55
  5196.2 1072.32  5220.6 1070.29  5340.6  1071.9  5900.1 1066.53  5949.6 1068.46
    5956 1070.61  6027.7 1069.67  6034.2 1071.06  6077.2 1073.14    6114 1073.66
#Mann= 3 ,-1 , 0
  3652.6     .05       0  4997.4     .05       0  5002.2     .05       0
#XS Ineff= 2 , 0
       0                  5196.2       0 1072.32
Permanent Ineff=
       F       F
Bank Sta=4997.4,5002.2
XS Rating Curve= 0 ,0
Exp/Cntr=0.3,0.1

Type RM Length L Ch R = 1 ,31117   ,449,449,449
BEGIN DESCRIPTION:
Mapping XS fa9ec640
END DESCRIPTION:
XS GIS Cut Line= 5
      2875094.53     10269835.47      2875157.03      10269231.3
      2875104.95     10268955.26      2874834.92     10268552.59
       2874597.4     10268271.15
#Sta/Elev= 30
  4192.8 1094.82  4196.5 1094.82  4205.2 1099.67  4215.3 1099.13  4325.9 1087.15
  4335.9 1087.44  4350.4 1083.49    4356 1080.61  4366.1 1078.61  4436.4 1079.39
  4687.8 1071.58  4748.1 1072.54  4930.6 1064.63    4951 1065.29  4981.5 1063.55
  4996.5 1064.58  4999.5 1063.42  4999.8 1062.92  5004.3 1063.42  5022.2 1065.36
  5079.7 1066.99  5182.3 1064.29  5420.8 1064.98    5671 1067.94  5728.2 1066.08
  5799.7 1068.22    5827 1070.83  5877.7  1069.7  5905.5 1072.24  5934.2 1072.48
#Mann= 3 ,-1 , 0
  4192.8     .05       0  4999.5     .05       0  5004.3     .05       0
#XS Ineff= 2 , 0
       0                  5079.7       0
Permanent Ineff=
       F       F
Bank Sta=4999.5,5004.3
XS Rating Curve= 0 ,0
Exp/Cntr=0.3,0.1

Type RM Length L Ch R = 1 ,30668   ,668,668,668
BEGIN DESCRIPTION:
Mapping XS f99f5e48
END DESCRIPTION:
XS GIS Cut Line= 4
       2875703.9     10269194.83      2875490.37     10268788.59
       2875261.2     10268616.72      2874870.66     10268429.25
#Sta/Elev= 30
  4380.1  1074.2  4506.3 1072.73  4574.1 1070.07  4585.7 1068.35    4608 1069.66
  4618.5 1068.52  4646.2 1068.94  4662.6 1067.36  4728.7 1065.39  4766.1 1064.96
  4794.9 1066.27  4816.9 1064.66  4874.7 1064.95  4889.2 1063.23  4895.5 1063.87
  4960.1 1062.59  5015.9 1059.51  5016.3 1059.01    5021 1059.51  5032.4 1061.65
  5095.5 1060.81  5163.9 1062.98  5214.8 1060.94  5265.6 1062.05  5320.2 1064.87
  5373.3 1066.15  5446.8 1065.77  5463.9 1067.37  5514.7  1068.6  5558.7 1066.15
#Mann= 3 ,-1 , 0
  4380.1     .05       0  5015.9     .05       0    5021     .05       0
Bank Sta=5015.9,5021
XS Rating Curve= 0 ,0
Exp/Cntr=0.3,0.1

Type RM Length L Ch R = 1 ,30000   ,500,500,500
BEGIN DESCRIPTION:
RED ROCK CREEK 60.0
END DESCRIPTION:
XS GIS Cut Line= 3
      2876155.66     10268853.08      2875505.15     10268056.04
      2874505.66      10267803.1
#Sta/Elev= 30
  3971.2 1077.41  4262.7 1071.87  4297.8  1072.8  4355.3 1069.79  4419.2 1072.54
  4425.6 1070.14    4440 1068.97    4547 1064.94  4617.3 1063.47  4717.9 1065.59
  4973.5 1057.45  4994.3 1054.93  5020.1 1056.16  5031.3 1054.52  5031.7 1054.02
  5036.6 1054.52  5040.7  1056.9    5157 1058.18  5257.3  1063.3  5267.6 1061.76
  5298.6 1061.66    5398 1063.69  5576.1  1066.4  5752.5 1068.73  5865.9 1071.92
  5896.9 1071.38  5925.9 1075.12    5931  1073.4  5958.8 1075.62    6031 1076.07
#Mann= 5 ,-1 , 0
  3971.2     .05       0  5031.3     .03       0  5036.6     .05       0
    5398     .12       0  5576.1     .05       0
Bank Sta=5031.3,5036.6
XS Rating Curve= 0 ,0
Exp/Cntr=0.3,0.1

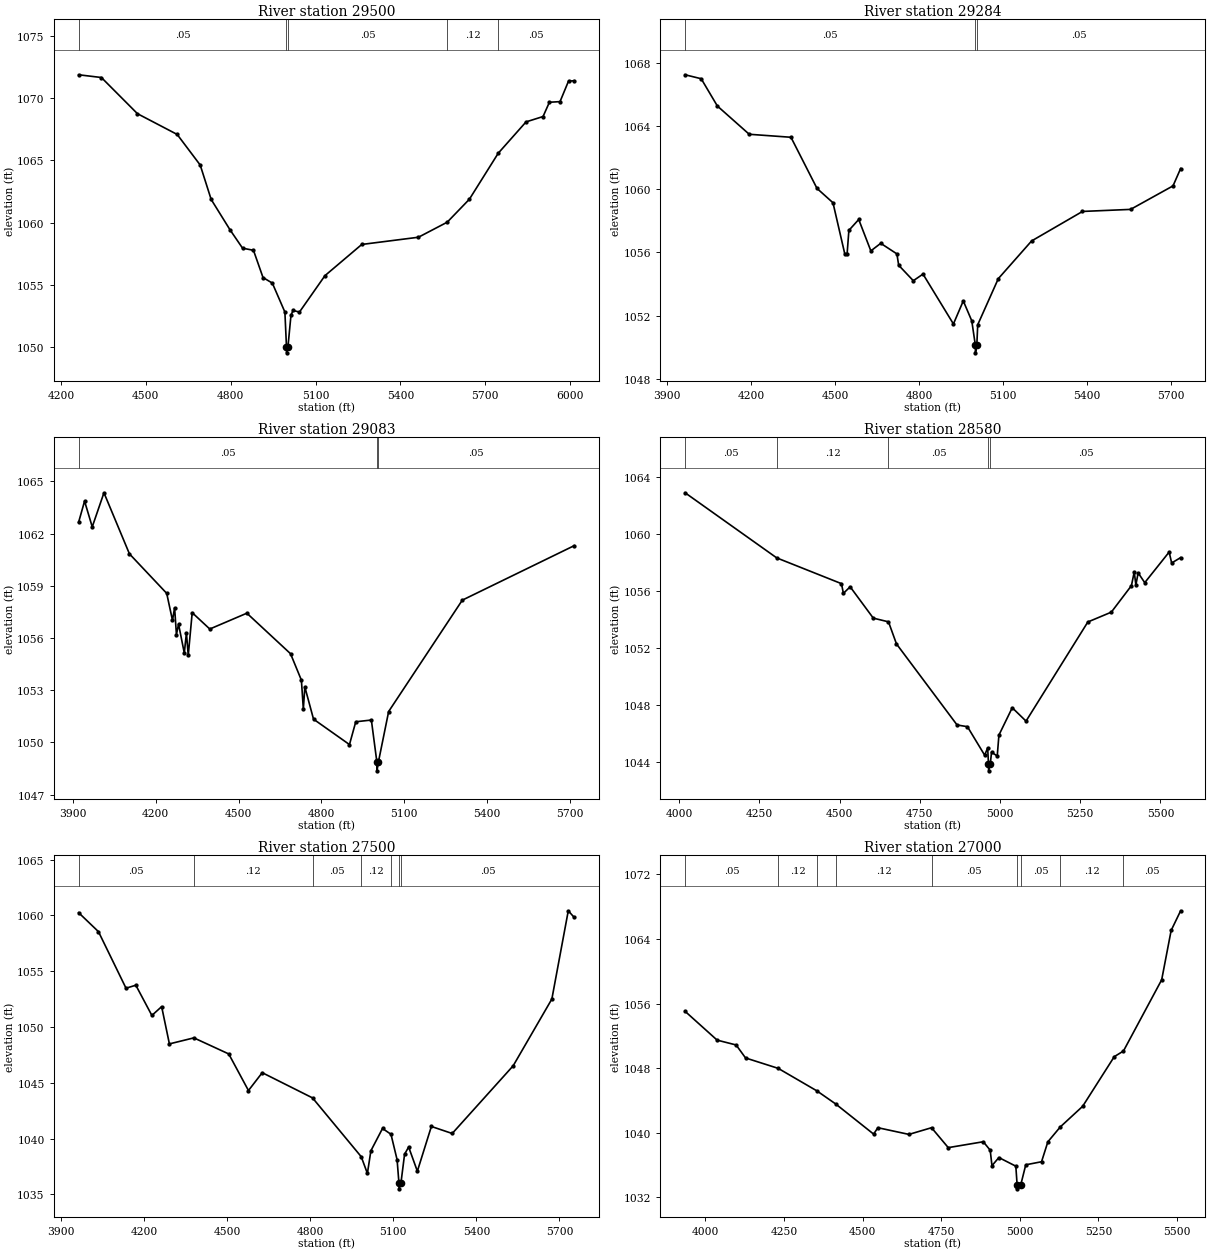
Type RM Length L Ch R = 1 ,29500   ,216,216,216
BEGIN DESCRIPTION:
RED ROCK CREEK 59.0
END DESCRIPTION:
XS GIS Cut Line= 3
      2876005.71     10268253.15      2875668.86     10267596.85
      2874655.72     10267653.11
#Sta/Elev= 30
  4262.3 1071.89  4342.8 1071.67  4470.3 1068.76  4610.8 1067.09  4692.2 1064.63
    4731 1061.86  4797.6 1059.42    4842 1057.94  4880.6 1057.77  4914.3 1055.58
  4947.3 1055.13  4991.7  1052.8  4997.3 1050.02  4997.7 1049.52  5002.6 1050.02
  5013.2 1052.54  5020.5 1052.93  5043.2  1052.8  5133.4 1055.73  5263.6 1058.24
  5463.9 1058.82  5565.7 1060.03  5644.2 1061.88  5746.2 1065.58  5844.5  1068.1
  5904.6 1068.53  5927.1 1069.68  5964.7 1069.73  5994.7 1071.38  6014.7 1071.41
#Mann= 5 ,-1 , 0
  4262.3     .05       0  4997.3     .05       0  5002.6     .05       0
  5565.7     .12       0  5746.2     .05       0
Bank Sta=4997.3,5002.6
XS Rating Curve= 0 ,0
Exp/Cntr=0.3,0.1

Type RM Length L Ch R = 1 ,29284   ,201,201,201
BEGIN DESCRIPTION:
Mapping XS 6088fd5f
END DESCRIPTION:
XS GIS Cut Line= 4
      2876422.63     10268147.94      2875917.45     10267507.34
      2875568.49      10267293.8      2875028.72     10267215.95
#Sta/Elev= 30
  3963.9 1067.26  4021.4 1067.01  4079.2 1065.28    4193 1063.49  4342.1  1063.3
  4435.1 1060.06  4492.2 1059.15  4534.5  1055.9  4542.6 1055.89    4549  1057.4
  4584.2 1058.09  4627.5  1056.1  4662.8 1056.58  4720.6 1055.91  4726.9 1055.19
  4779.2 1054.21  4813.8 1054.63  4922.5 1051.47  4957.7 1052.93    4988 1051.67
  5000.7 1050.14  5001.2 1049.64  5006.1 1050.14  5009.3 1051.42  5082.8 1054.34
  5201.8 1056.73  5383.6  1058.6  5555.4 1058.73    5707 1060.22  5734.2 1061.32
#Mann= 3 ,-1 , 0
  3963.9     .05       0  5000.7     .03       0  5006.1     .05       0
Bank Sta=5000.7,5006.1
XS Rating Curve= 0 ,0
Exp/Cntr=0.3,0.1

Type RM Length L Ch R = 1 ,29083   ,503,503,503
BEGIN DESCRIPTION:
Mapping XS b8cc62c5
END DESCRIPTION:
XS GIS Cut Line= 5
      2876677.84     10267840.64      2876349.74     10267455.26
      2875922.66     10267262.55      2875604.95     10267111.51
      2875148.36     10267007.74
#Sta/Elev= 30
  3920.9 1062.66  3942.4 1063.87  3970.2 1062.39  4012.6 1064.35  4104.9 1060.84
  4239.9 1058.57  4260.8 1057.02  4268.5 1057.74  4275.1  1056.2  4282.8  1056.8
  4303.6 1055.14  4311.3  1056.3  4317.9    1055  4332.2 1057.46  4395.9 1056.52
  4530.2 1057.43  4688.4  1055.1  4727.7 1053.58  4734.7 1051.92  4740.2 1053.19
  4771.6 1051.34  4901.8 1049.88  4924.6 1051.19  4981.1 1051.29  5001.1 1048.87
  5001.5 1048.37  5006.5 1048.87  5043.7 1051.78  5310.5 1058.18  5715.6 1061.31
#Mann= 3 ,-1 , 0
  3920.9     .05       0  5001.1     .03       0  5006.5     .05       0
Bank Sta=5001.1,5006.5
XS Rating Curve= 0 ,0
Exp/Cntr=0.3,0.1

Type RM Length L Ch R = 1 ,28580   ,1080,1080,1080
BEGIN DESCRIPTION:
Mapping XS 9821a477
END DESCRIPTION:
XS GIS Cut Line= 5
      2876792.44     10267444.83      2876537.24     10267085.47
      2876214.32     10266871.92      2875844.53     10266726.09
      2875538.94     10266819.32
#Sta/Elev= 30
  4018.2  1062.9  4303.8 1058.33  4505.7 1056.52  4511.7 1055.84  4532.8  1056.3
  4604.9  1054.1  4652.3 1053.84  4677.2 1052.29  4866.1  1046.6  4898.4 1046.48
  4952.1 1044.48  4961.5 1044.99    4964 1043.88  4964.5 1043.38  4969.7 1043.88
  4973.6 1044.69  4991.3 1044.42  4996.6 1045.89  5038.1 1047.81  5081.1 1046.87
  5273.8 1053.83    5347 1054.52  5409.7 1056.38  5418.4 1057.34  5423.6 1056.43
  5430.6 1057.28  5451.2 1056.59  5527.3 1058.74  5535.1 1057.97  5563.1 1058.35
#Mann= 5 ,-1 , 0
  4018.2     .05       0  4303.8     .12       0  4652.3     .05       0
    4964     .03       0  4969.7     .05       0
Bank Sta=4964,4969.7
XS Rating Curve= 0 ,0
Exp/Cntr=0.3,0.1

Type RM Length L Ch R = 1 ,27500   ,500,500,500
BEGIN DESCRIPTION:
RED ROCK CREEK 55.0
END DESCRIPTION:
XS GIS Cut Line= 3
      2877455.65     10266653.09       2876633.5     10266021.07
       2876405.7     10265303.15
#Sta/Elev= 30
    3963 1060.24  4034.6 1058.54  4134.2 1053.47  4169.6 1053.74  4227.6 1051.03
  4262.9 1051.82  4290.9 1048.48  4379.3 1049.02  4505.3 1047.58  4576.5  1044.3
  4626.3  1045.9    4808 1043.64  4983.9 1038.37  5006.2 1036.87  5018.8  1038.9
  5060.8  1040.9  5091.4 1040.38  5113.5  1038.1  5120.2 1035.99  5120.7 1035.49
  5127.3 1035.99  5140.5 1038.59  5155.2 1039.24  5186.7 1037.07  5237.3 1041.08
  5312.6 1040.45  5532.9 1046.52  5672.6  1052.5  5731.9 1060.41  5753.2 1059.82
#Mann= 7 ,-1 , 0
    3963     .05       0  4379.3     .12       0    4808     .05       0
  4983.9     .12       0  5091.4     .05       0  5120.2     .07       0
  5127.3     .05       0
Bank Sta=5120.2,5127.3
XS Rating Curve= 0 ,0
Exp/Cntr=0.3,0.1

Type RM Length L Ch R = 1 ,27000   ,500,500,500
BEGIN DESCRIPTION:
RED ROCK CREEK 54.0
END DESCRIPTION:
XS GIS Cut Line= 3
      2877405.69     10266553.11      2876908.33     10265612.17
      2876855.68     10265103.09
#Sta/Elev= 30
  3935.7 1055.03  4037.6 1051.46    4098 1050.86    4128 1049.25  4231.8 1047.96
  4354.8 1045.17  4414.5 1043.55  4535.2 1039.81  4548.9  1040.6  4647.6 1039.77
  4719.5  1040.6  4772.7 1038.13  4884.1 1038.86  4906.1 1037.81  4911.7 1035.89
  4933.7  1036.9  4987.6 1035.83  4991.7 1033.52  4992.2 1033.02  5003.3 1033.52
  5019.2    1036  5069.4 1036.38  5089.5 1038.85  5129.1  1040.7  5200.1 1043.25
  5300.7 1049.41  5329.9 1050.11  5451.5 1058.94  5481.6 1065.06  5511.8  1067.5
#Mann= 9 ,-1 , 0
  3935.7     .05       0  4231.8     .12       0  4354.8     .05       0
  4414.5     .12       0  4719.5     .05       0  4991.7     .05       0
  5003.3     .05       0  5129.1     .12       0  5329.9     .05       0
Bank Sta=4991.7,5003.3
XS Rating Curve= 0 ,0
Exp/Cntr=0.3,0.1

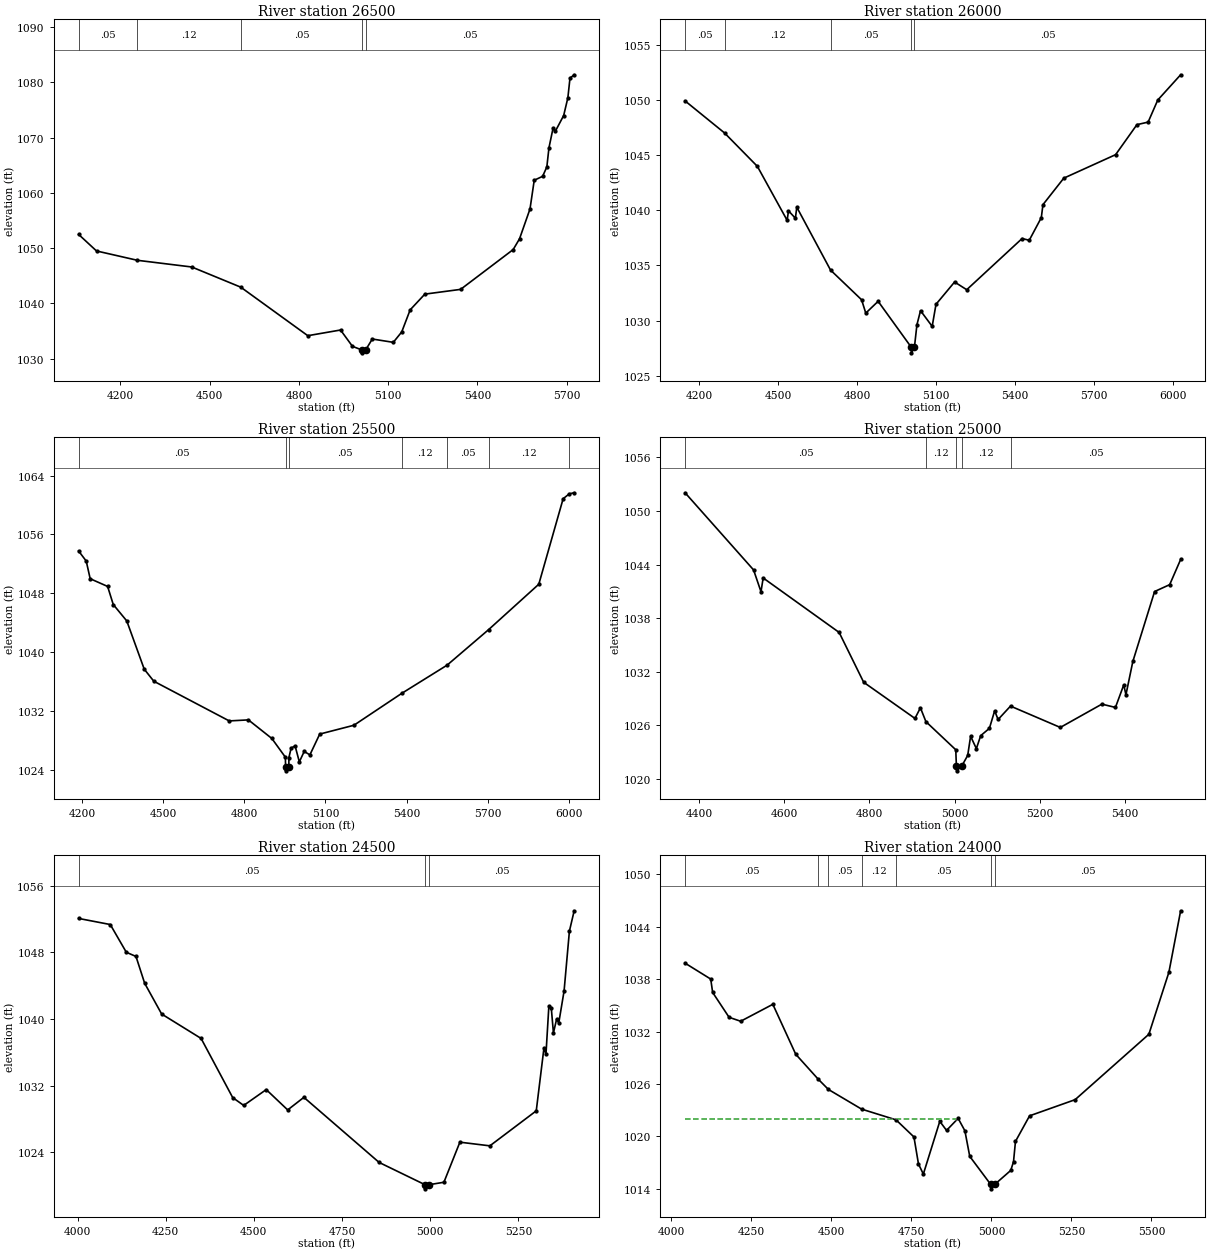
Type RM Length L Ch R = 1 ,26500   ,500,500,500
BEGIN DESCRIPTION:
RED ROCK CREEK 53.0
END DESCRIPTION:
XS GIS Cut Line= 3
      2877405.68     10266453.13      2877371.62     10265513.05
      2876855.69     10265003.12
#Sta/Elev= 30
  4059.3 1052.47  4119.4 1049.48  4256.8 1047.79  4439.6 1046.58  4604.4 1042.93
  4829.8 1034.15  4939.9 1035.18  4979.9 1032.23  5012.5 1031.55    5013 1031.05
  5024.1 1031.55  5046.6 1033.55  5117.3 1032.95  5145.6 1034.83  5173.9 1038.82
  5223.3 1041.67  5343.6 1042.53  5520.3 1049.73  5541.6 1051.67  5576.9 1057.08
  5591.1 1062.27  5619.3 1062.98  5633.5 1064.68  5640.6 1068.13  5654.7 1071.77
  5661.8 1071.11  5690.1 1073.98  5704.2 1077.19  5711.3 1080.74  5725.4 1081.35
#Mann= 5 ,-1 , 0
  4059.3     .05       0  4256.8     .12       0  4604.4     .05       0
  5012.5     .05       0  5024.1     .05       0
Bank Sta=5012.5,5024.1
XS Rating Curve= 0 ,0
Exp/Cntr=0.3,0.1

Type RM Length L Ch R = 1 ,26000   ,500,500,500
BEGIN DESCRIPTION:
RED ROCK CREEK 52.0
END DESCRIPTION:
XS GIS Cut Line= 3
       2877555.7     10266203.07      2877829.68     10265394.11
      2876955.67     10264853.11
#Sta/Elev= 30
  4145.9  1049.9  4295.6    1047  4420.4 1043.97  4533.4 1039.08  4538.6 1039.94
  4564.8 1039.27  4570.1 1040.27  4698.3 1034.57  4816.2 1031.88  4832.1 1030.67
    4879 1031.74  5005.1 1027.57  5005.6 1027.07  5016.8 1027.57  5026.4 1029.62
    5040 1030.89  5084.3 1029.47  5098.8 1031.47  5169.4 1033.49  5215.5 1032.79
  5425.8 1037.43  5452.9 1037.27  5498.7 1039.32    5505  1040.5  5584.1  1042.9
  5780.9 1045.03  5861.9 1047.75  5904.4 1047.98    5941 1049.98  6027.9 1052.27
#Mann= 5 ,-1 , 0
  4145.9     .05       0  4295.6     .12       0  4698.3     .05       0
  5005.1     .05       0  5016.8     .05       0
Bank Sta=5005.1,5016.8
XS Rating Curve= 0 ,0
Exp/Cntr=0.3,0.1

Type RM Length L Ch R = 1 ,25500   ,500,500,500
BEGIN DESCRIPTION:
RED ROCK CREEK 51.0
END DESCRIPTION:
XS GIS Cut Line= 3
       2878805.7     10265953.14      2878315.87     10265304.64
      2878505.69     10264303.07
#Sta/Elev= 30
  4187.3 1053.74  4215.4 1052.37    4230 1049.97  4294.5 1048.92  4315.3 1046.46
  4365.3 1044.23  4429.8 1037.67  4465.2 1036.03  4744.1 1030.63  4814.9 1030.77
  4901.7 1028.24  4951.8 1025.69  4952.3 1024.34  4952.8 1023.84  4964.5 1024.34
  4964.7 1025.64    4973 1026.94  4987.6 1027.23  5003.3 1025.06  5021.3 1026.48
  5042.3 1026.01  5078.7 1028.84  5205.1 1030.04    5382 1034.38  5549.8 1038.22
  5703.2 1043.05  5888.6 1049.22  5978.6 1060.85  6001.4 1061.52  6019.4 1061.66
#Mann= 7 ,-1 , 0
  4187.3     .05       0  4952.3     .03       0  4964.5     .05       0
    5382     .12       0  5549.8     .05       0  5703.2     .12       0
  6001.4     .05       0
Bank Sta=4952.3,4964.5
XS Rating Curve= 0 ,0
Exp/Cntr=0.3,0.1

Type RM Length L Ch R = 1 ,25000   ,500,500,500
BEGIN DESCRIPTION:
RED ROCK CREEK 50.0
END DESCRIPTION:
XS GIS Cut Line= 3
      2878855.68     10265903.11      2878803.13       10265273.
      2878905.68     10264753.12
#Sta/Elev= 30
  4367.7 1052.04  4528.3  1043.4  4545.7 1040.96  4550.8  1042.5    4729  1036.4
  4786.5 1030.82  4906.8 1026.77  4919.6 1027.96  4932.5 1026.41  5002.5 1023.26
    5004  1021.4  5004.5  1020.9  5016.2  1021.4  5030.5 1022.63  5037.3 1024.77
  5050.8 1023.39    5061 1024.84  5081.4 1025.66  5093.7 1027.62  5101.8 1026.65
  5130.9 1028.15  5247.7 1025.76  5345.2 1028.37    5377    1028  5396.5 1030.53
  5401.6 1029.42  5417.8 1033.15  5468.8 1040.98  5504.2 1041.75  5529.9 1044.57
#Mann= 5 ,-1 , 0
  4367.7     .05       0  4932.5     .12       0    5004     .07       0
  5016.2     .12       0  5130.9     .05       0
Bank Sta=5004,5016.2
XS Rating Curve= 0 ,0
Exp/Cntr=0.3,0.1

Type RM Length L Ch R = 1 ,24500   ,500,500,500
BEGIN DESCRIPTION:
RED ROCK CREEK 49.0
END DESCRIPTION:
XS GIS Cut Line= 3
      2878955.69      10266003.1      2879229.26     10265044.57
      2879005.71     10264703.15
#Sta/Elev= 30
  4003.2 1052.07  4092.9 1051.34  4138.4 1048.01  4165.8 1047.51  4190.4 1044.29
  4238.6  1040.6  4350.4 1037.67    4440 1030.57  4471.2 1029.63  4535.1 1031.53
  4595.9 1029.09  4641.8  1030.6  4855.1 1022.79    4985 1020.12  4985.5 1019.62
  4997.2 1020.12  5038.8 1020.41  5084.1 1025.22  5169.1 1024.78  5300.6 1028.98
  5322.3 1036.48  5328.2 1035.82  5336.4 1041.58  5343.3 1041.28  5349.3 1038.33
  5358.4    1040  5364.4 1039.52  5379.5 1043.37  5394.6 1050.55  5408.1 1052.99
#Mann= 3 ,-1 , 0
  4003.2     .05       0    4985     .05       0  4997.2     .05       0
Bank Sta=4985,4997.2
XS Rating Curve= 0 ,0
Exp/Cntr=0.3,0.1

Type RM Length L Ch R = 1 ,24000   ,500,500,500
BEGIN DESCRIPTION:
RED ROCK CREEK 48.0
END DESCRIPTION:
XS GIS Cut Line= 3
      2880205.69     10265653.12      2879684.65     10264850.04
      2879205.69     10264503.12
#Sta/Elev= 30
  4042.7 1039.84  4122.8 1038.02  4128.8 1036.49  4180.2 1033.64  4216.4 1033.19
  4316.9 1035.13  4388.5 1029.41  4458.1 1026.58  4490.6 1025.38  4594.2 1023.13
  4701.9  1021.9  4757.9 1019.94  4772.1 1016.84  4787.3 1015.69  4838.7 1021.73
  4859.8 1020.69    4896 1022.07  4917.1 1020.65  4932.3 1017.72  4997.9  1014.5
  4998.4    1014  5010.2  1014.5  5060.5 1016.11  5069.1 1017.11  5075.2 1019.43
  5119.3 1022.36  5261.6 1024.21  5492.1  1031.7  5554.7  1038.8  5591.4 1045.84
#Mann= 7 ,-1 , 0
  4042.7     .05       0  4458.1     .12       0  4490.6     .05       0
  4594.2     .12       0  4701.9     .05       0  4997.9     .05       0
  5010.2     .05       0
#XS Ineff= 2 , 0
       0    4889    1022               0
Permanent Ineff=
       F       F
Bank Sta=4997.9,5010.2
XS Rating Curve= 0 ,0
Exp/Cntr=0.3,0.1