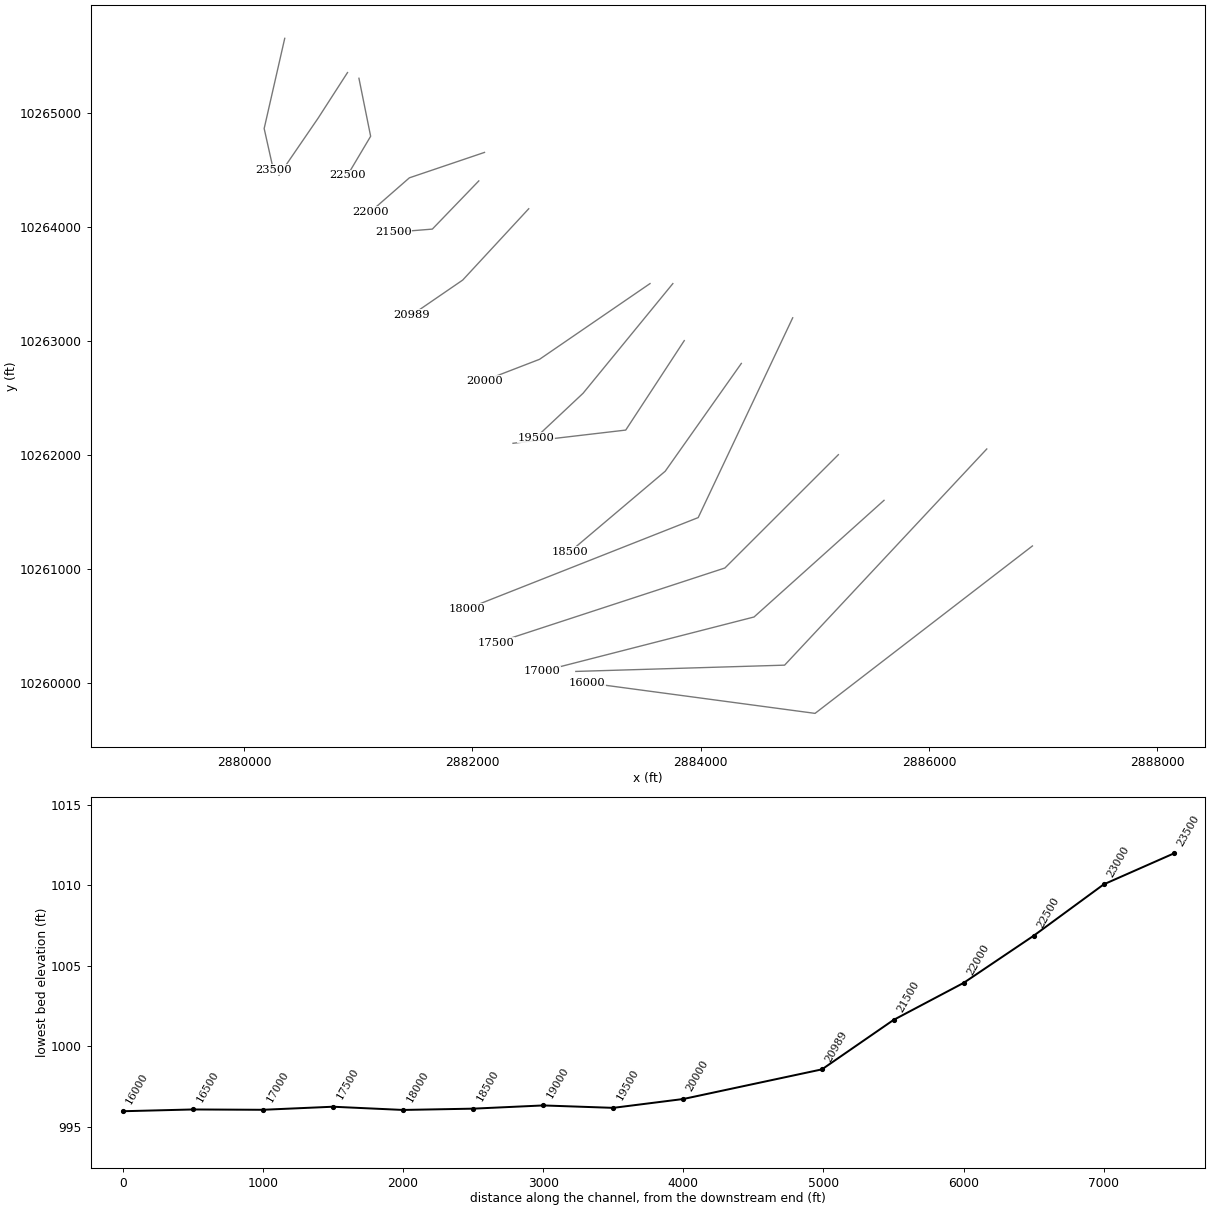
HEC-RAS study RED ROCK CREEK.prj: RED ROCK CREEK Base Level Engineering

--- RED ROCK CREEK.g01 (geometry) --- (continued)

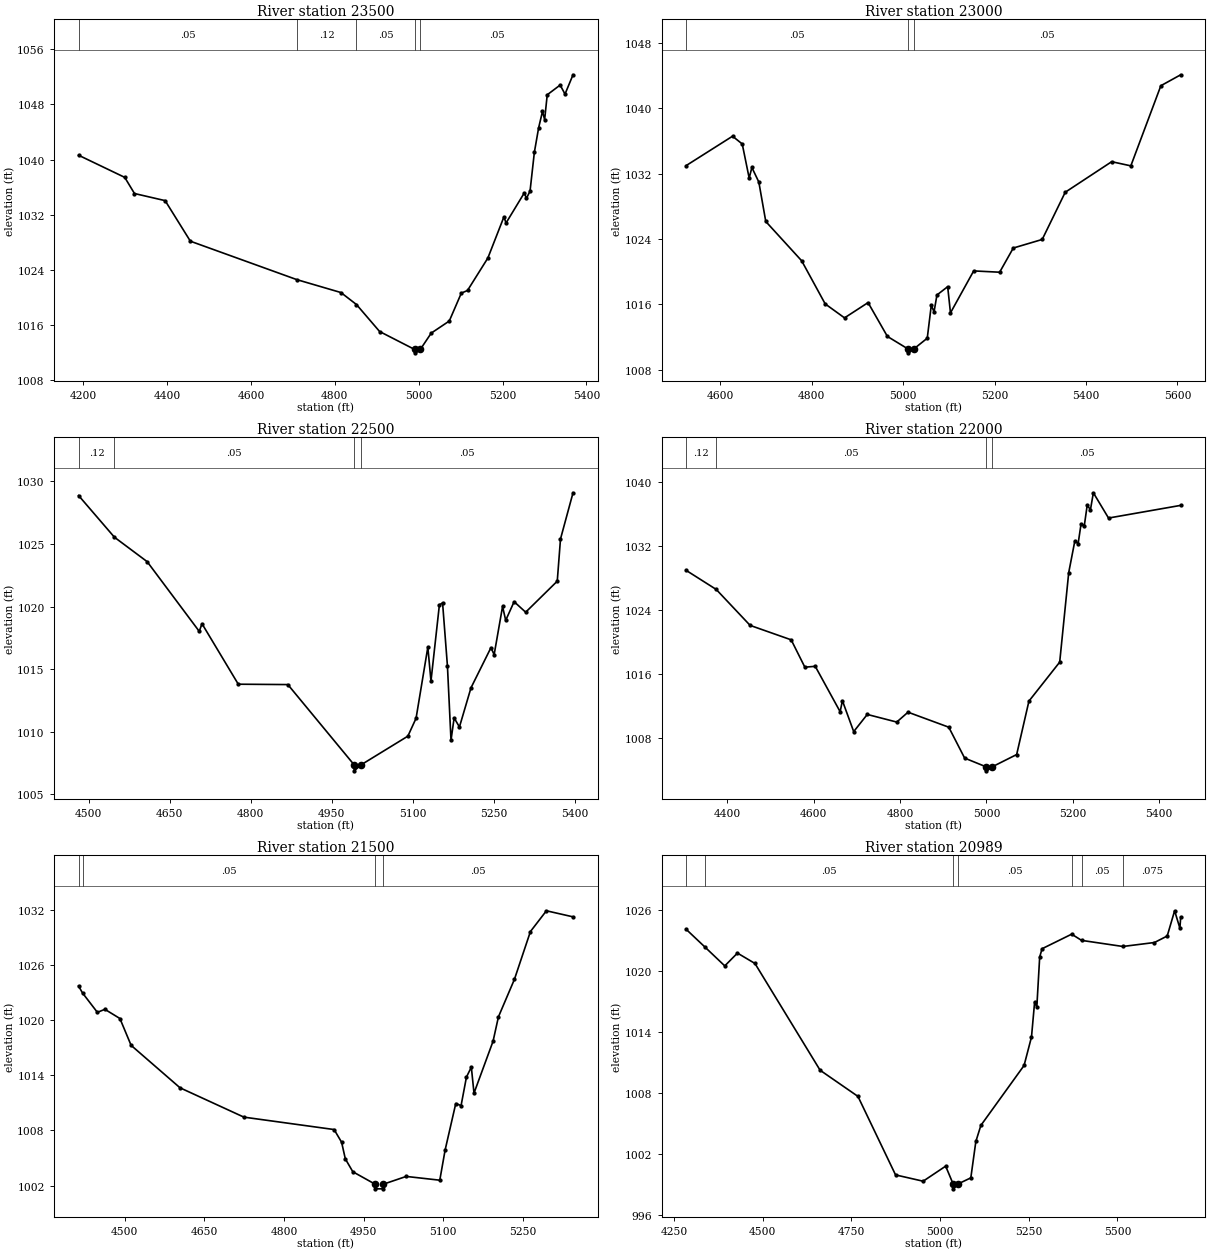
Type RM Length L Ch R = 1 ,23500   ,500,500,500
BEGIN DESCRIPTION:
RED ROCK CREEK 47.0
END DESCRIPTION:
XS GIS Cut Line= 3
      2880355.68     10265653.08      2880175.44     10264862.26
      2880255.68     10264503.12
#Sta/Elev= 30
  4188.9 1040.63    4299 1037.42  4322.2 1035.08  4395.3 1034.05  4455.5 1028.17
  4709.4  1022.6  4814.5 1020.73  4851.6 1018.99  4906.8 1015.08    4990 1012.49
  4990.5 1011.99  5003.9 1012.49  5029.9 1014.85  5072.9  1016.6  5101.6 1020.64
  5116.4 1021.03  5164.9 1025.73  5203.2 1031.69  5208.3 1030.81  5251.8 1035.17
  5256.9 1034.38  5265.5 1035.43  5275.8 1041.05    5286 1044.61  5295.2 1046.98
  5300.3 1045.79  5306.5 1049.39  5337.3  1050.8  5348.9 1049.49    5368 1052.29
#Mann= 5 ,-1 , 0
  4188.9     .05       0  4709.4     .12       0  4851.6     .05       0
    4990     .03       0  5003.9     .05       0
Bank Sta=4990,5003.9
XS Rating Curve= 0 ,0
Exp/Cntr=0.3,0.1

Type RM Length L Ch R = 1 ,23000   ,500,500,500
BEGIN DESCRIPTION:
RED ROCK CREEK 46.0
END DESCRIPTION:
XS GIS Cut Line= 3
      2880905.69     10265353.12      2880648.65     10264954.03
      2880305.67     10264453.09
#Sta/Elev= 30
  4525.3    1033  4626.6 1036.59  4647.8 1035.64    4663 1031.46  4668.9 1032.76
  4684.1 1030.98  4699.3 1026.15  4777.8 1021.34  4829.3 1016.06  4871.6 1014.35
  4923.1 1016.22  4965.4 1012.08  5009.7 1010.57  5010.2 1010.07  5023.7 1010.57
  5052.6 1011.86  5061.4 1015.88  5067.5  1015.1  5073.8 1017.15  5097.3 1018.17
  5103.4 1014.96  5154.2  1020.1    5211 1019.94  5240.8  1022.9  5304.1 1023.95
  5354.5 1029.73  5456.1 1033.47    5498 1032.96  5563.7 1042.77  5607.1 1044.11
#Mann= 3 ,-1 , 0
  4525.3     .05       0  5009.7     .03       0  5023.7     .05       0
Bank Sta=5009.7,5023.7
XS Rating Curve= 0 ,0
Exp/Cntr=0.3,0.1

Type RM Length L Ch R = 1 ,22500   ,500,500,500
BEGIN DESCRIPTION:
RED ROCK CREEK 45.0
END DESCRIPTION:
XS GIS Cut Line= 3
      2881005.69      10265303.1      2881108.26     10264794.43
      2880905.69     10264453.12
#Sta/Elev= 30
  4481.1 1028.87  4547.5 1025.54  4608.1 1023.59  4704.6 1018.02  4709.7 1018.63
  4776.9  1013.8  4868.7 1013.77  4991.1 1007.38  4991.6 1006.88  5005.1 1007.38
    5091 1009.65  5106.2 1011.08    5128 1016.76  5133.8 1014.05  5149.4 1020.14
  5155.3 1020.29  5164.3 1015.25  5170.9 1009.32  5176.7 1011.11  5186.5 1010.38
  5207.9 1013.51  5244.9 1016.72  5250.8 1016.16  5266.4 1020.01  5272.2  1018.9
  5287.8 1020.39  5309.2 1019.55  5367.7 1022.03  5373.7  1025.4  5396.9 1029.09
#Mann= 4 ,-1 , 0
  4481.1     .12       0  4547.5     .05       0  4991.1     .03       0
  5005.1     .05       0
Bank Sta=4991.1,5005.1
XS Rating Curve= 0 ,0
Exp/Cntr=0.3,0.1

Type RM Length L Ch R = 1 ,22000   ,500,500,500
BEGIN DESCRIPTION:
RED ROCK CREEK 44.0
END DESCRIPTION:
XS GIS Cut Line= 3
      2882105.66      10264653.1      2881447.77      10264430.3
      2881109.21     10264134.46
#Sta/Elev= 30
  4305.4 1028.93  4374.8 1026.56  4453.2 1022.08  4548.2 1020.28  4579.9 1016.87
  4603.9 1016.98  4661.5 1011.32  4666.8 1012.69  4692.9 1008.84  4724.3 1010.98
  4792.5 1010.03  4818.6 1011.26  4912.9 1009.39  4949.6 1005.54  4999.3 1004.45
  4999.8 1003.95  5013.4 1004.45    5070 1005.98  5098.4 1012.64  5169.6  1017.5
  5190.5 1028.67  5204.7 1032.62  5212.3 1032.28    5219 1034.72  5226.6 1034.53
  5233.2 1037.04  5240.8 1036.51  5247.5 1038.61  5282.6 1035.46  5449.6 1037.04
#Mann= 4 ,-1 , 0
  4305.4     .12       0  4374.8     .05       0  4999.3     .03       0
  5013.4     .05       0
Bank Sta=4999.3,5013.4
XS Rating Curve= 0 ,0
Exp/Cntr=0.3,0.1

Type RM Length L Ch R = 1 ,21500   ,511,511,511
BEGIN DESCRIPTION:
RED ROCK CREEK 43.0
END DESCRIPTION:
XS GIS Cut Line= 3
      2882055.69     10264403.12       2881648.7     10263980.68
      2881305.71     10263953.11
#Sta/Elev= 30
  4413.4 1023.71  4420.8 1022.96  4448.8 1020.85  4462.9 1021.18  4491.2 1020.18
  4512.3 1017.26  4604.4 1012.64  4724.6 1009.45  4894.4  1008.1  4908.5 1006.72
  4915.5 1004.91  4929.6 1003.51  4971.8 1002.15  4972.3 1001.65  4986.3 1001.65
  4986.8 1002.15  5030.1    1003  5093.3 1002.59  5103.4 1005.89  5123.4 1010.93
  5133.4 1010.71  5143.5 1013.81  5152.7 1014.89  5157.7 1012.06  5193.6 1017.71
  5203.7 1020.36  5233.8 1024.44  5263.9 1029.64    5294  1031.9  5344.1 1031.24
#Mann= 4 ,-1 , 0
  4413.4     .12       0  4420.8     .05       0  4971.8     .03       0
  4986.8     .05       0
Bank Sta=4971.8,4986.8
XS Rating Curve= 0 ,0
Exp/Cntr=0.3,0.1

Type RM Length L Ch R = 1 ,20989   ,989,989,989
BEGIN DESCRIPTION:
Mapping XS 86252722
END DESCRIPTION:
XS GIS Cut Line= 3
      2882493.13      10264159.2      2881915.01     10263534.21
      2881467.97     10263227.52
#Sta/Elev= 30
  4284.7 1024.09  4337.5 1022.35  4393.3  1020.5    4429 1021.76  4478.3 1020.74
    4662 1010.24  4768.6 1007.67  4874.6  999.95  4952.3  999.33  5015.8 1000.81
  5036.6  999.08  5037.1  998.58  5051.8  999.08  5086.7  999.66  5100.9 1003.24
  5115.1 1004.82  5236.8 1010.71  5257.7 1013.51  5266.6 1016.97  5272.7 1016.45
  5280.8 1021.38  5287.6 1022.19  5370.9 1023.62  5398.8 1023.01  5515.2 1022.41
  5604.3  1022.8  5640.2 1023.44  5661.1 1025.92    5676  1024.2  5678.2  1025.3
#Mann= 7 ,-1 , 0
  4284.7     .12       0  4337.5     .05       0  5036.6     .03       0
  5051.8     .05       0  5370.9    .075       0  5398.8     .05       0
  5515.2    .075       0
Bank Sta=5036.6,5051.8
XS Rating Curve= 0 ,0
Exp/Cntr=0.3,0.1

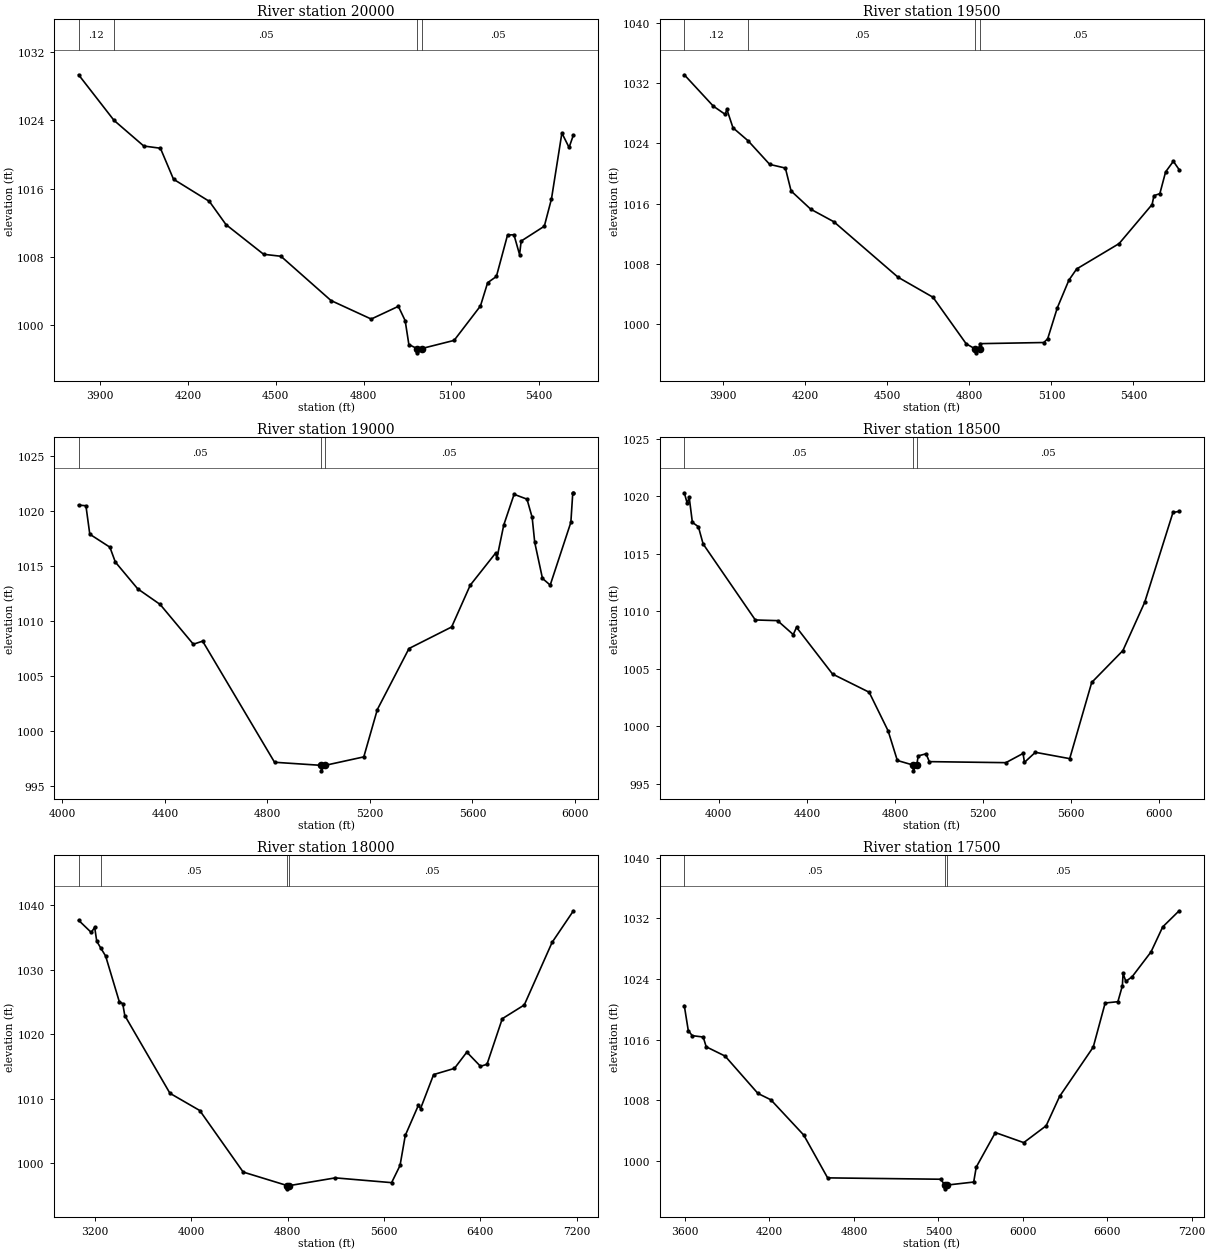
Type RM Length L Ch R = 1 ,20000   ,500,500,500
BEGIN DESCRIPTION:
RED ROCK CREEK 40.0
END DESCRIPTION:
XS GIS Cut Line= 3
      2883555.65     10263503.09      2882587.84     10262839.25
      2882105.72     10262653.12
#Sta/Elev= 30
  3826.4 1029.33  3947.3 1023.99    4049 1020.98  4105.9 1020.72  4150.6 1017.09
  4273.1 1014.49  4329.9 1011.77  4458.5 1008.29  4517.6 1008.06  4688.6 1002.87
    4826  1000.7  4918.7 1002.19    4942 1000.51  4954.6  997.71  4982.7  997.24
  4983.2  996.74  4998.2  997.24  5109.2   998.2  5199.1 1002.23  5223.7 1004.96
  5253.6 1005.69  5291.7 1010.55  5313.6 1010.58  5332.8 1008.25  5338.2 1009.84
  5417.3 1011.58  5441.8 1014.79  5477.3  1022.5  5501.9 1020.81  5516.8 1022.28
#Mann= 4 ,-1 , 0
  3826.4     .12       0  3947.3     .05       0  4982.7     .03       0
  4998.2     .05       0
Bank Sta=4982.7,4998.2
XS Rating Curve= 0 ,0
Exp/Cntr=0.3,0.1

Type RM Length L Ch R = 1 ,19500   ,500,500,500
BEGIN DESCRIPTION:
RED ROCK CREEK 39.0
END DESCRIPTION:
XS GIS Cut Line= 3
      2883755.66     10263503.08      2882969.13     10262541.47
      2882555.71     10262153.14
#Sta/Elev= 30
  3757.7 1033.12  3863.9 1028.95    3907 1027.87  3913.4 1028.52  3935.7 1026.08
  3991.4 1024.34  4069.9 1021.22  4127.3 1020.73  4148.2 1017.69  4219.9 1015.27
  4304.6  1013.6  4539.4 1006.23  4667.2 1003.57  4788.5  997.39  4822.3  996.69
  4822.8  996.19  4837.9  996.69    4838  997.41  5072.2  997.56  5086.4  998.05
  5121.6 1002.16    5164 1005.84  5192.4 1007.33  5347.7  1010.7  5468.3 1015.89
  5475.2 1017.07  5496.6 1017.33  5517.7 1020.22    5546 1021.63  5567.2 1020.52
#Mann= 4 ,-1 , 0
  3757.7     .12       0  3991.4     .05       0  4822.3     .03       0
  4837.9     .05       0
Bank Sta=4822.3,4837.9
XS Rating Curve= 0 ,0
Exp/Cntr=0.3,0.1

Type RM Length L Ch R = 1 ,19000   ,500,500,500
BEGIN DESCRIPTION:
RED ROCK CREEK 38.0
END DESCRIPTION:
XS GIS Cut Line= 3
      2883855.66     10263003.08      2883342.98      10262218.9
      2882355.65     10262103.11
#Sta/Elev= 30
  4063.1 1020.52  4091.7 1020.46  4106.8 1017.87  4185.2 1016.69  4206.4 1015.34
  4293.8  1012.9  4381.3 1011.48  4510.9 1007.86  4547.1 1008.14  4827.7  997.12
  5009.6  996.84  5010.1  996.34  5025.2  996.84    5176  997.61  5228.9 1001.92
  5352.4 1007.47  5518.8 1009.43  5591.3 1013.23  5690.3 1016.15  5695.3 1015.67
  5722.2 1018.71  5762.5  1021.5  5812.8 1021.06    5833  1019.4    5843 1017.13
  5873.2 1013.85  5903.4 1013.24    5984 1018.95  5991.5 1021.64  5994.1 1021.64
#Mann= 3 ,-1 , 0
  4063.1     .05       0  5009.6     .03       0  5025.2     .05       0
Bank Sta=5009.6,5025.2
XS Rating Curve= 0 ,0
Exp/Cntr=0.3,0.1

Type RM Length L Ch R = 1 ,18500   ,500,500,500
BEGIN DESCRIPTION:
RED ROCK CREEK 37.0
END DESCRIPTION:
XS GIS Cut Line= 3
      2884355.66     10262803.08      2883688.78     10261857.98
      2882855.66     10261153.09
#Sta/Elev= 30
  3843.3  1020.3  3856.8 1019.37  3865.4 1019.93    3880 1017.73  3907.3 1017.35
  3928.9 1015.85  4165.9 1009.25  4266.9 1009.19  4338.3 1007.98  4353.1 1008.61
  4516.8 1004.55  4683.1 1002.97  4769.3  999.61  4811.1  997.04  4883.1  996.64
  4883.6  996.14  4899.3  996.64  4905.9  997.44  4941.6  997.62  4956.4  996.94
  5304.1  996.85  5382.1  997.65  5388.7  996.88  5438.1  997.75  5594.1   997.2
  5694.1 1003.82  5835.8 1006.59  5934.7 1010.78  6063.3 1018.59  6091.3 1018.68
#Mann= 3 ,-1 , 0
  3843.3     .05       0  4883.1     .03       0  4899.3     .05       0
Bank Sta=4883.1,4899.3
XS Rating Curve= 0 ,0
Exp/Cntr=0.3,0.1

Type RM Length L Ch R = 1 ,18000   ,500,500,500
BEGIN DESCRIPTION:
RED ROCK CREEK 36.0
END DESCRIPTION:
XS GIS Cut Line= 3
      2884805.68      10263203.1      2883977.72     10261451.75
      2881955.72     10260653.13
#Sta/Elev= 30
  3062.8 1037.69    3168  1035.8  3196.3  1036.6  3213.5 1034.45  3245.1 1033.44
  3287.3 1032.15  3401.1 1025.06  3429.4 1024.77  3446.6 1022.92  3821.8 1010.87
  4069.4  1008.2  4430.2  998.66  4797.1  996.56  4797.6  996.06  4813.7  996.56
  5195.4  997.76  5663.3  997.02  5733.3  999.68  5776.9 1004.34  5885.1 1008.98
  5904.1 1008.51  6012.3 1013.77  6185.3 1014.73  6288.2 1017.25  6401.8 1015.05
  6455.9 1015.37  6582.7 1022.43  6765.5 1024.56  6996.9 1034.27    7174 1039.16
#Mann= 4 ,-1 , 0
  3062.8     .12       0  3245.1     .05       0  4797.1     .03       0
  4813.7     .05       0
Bank Sta=4797.1,4813.7
XS Rating Curve= 0 ,0
Exp/Cntr=0.3,0.1

Type RM Length L Ch R = 1 ,17500   ,500,500,500
BEGIN DESCRIPTION:
RED ROCK CREEK 35.0
END DESCRIPTION:
XS GIS Cut Line= 3
      2885205.71     10262003.14      2884211.72     10261009.88
      2882205.69     10260353.11
#Sta/Elev= 30
  3594.8 1020.48  3623.1 1017.18  3651.4 1016.51  3729.2 1016.33  3750.4 1015.04
  3884.8 1013.81  4118.1 1008.87    4210 1008.03  4443.4 1003.37  4613.1  997.71
  5416.7  997.53  5446.2  996.76  5446.7  996.26  5462.9  996.76    5651  997.16
  5669.3  999.14    5805  1003.7  6006.6 1002.37  6165.9  1004.6  6261.4 1008.48
  6500.5    1015  6585.2 1020.83  6675.5    1021  6707.4  1023.1  6712.6 1024.74
    6732 1023.69  6776.4 1024.29  6910.9 1027.58  6994.1 1030.89  7110.8 1033.02
#Mann= 3 ,-1 , 0
  3594.8     .05       0  5446.2     .03       0  5462.9     .05       0
Bank Sta=5446.2,5462.9
XS Rating Curve= 0 ,0
Exp/Cntr=0.3,0.1

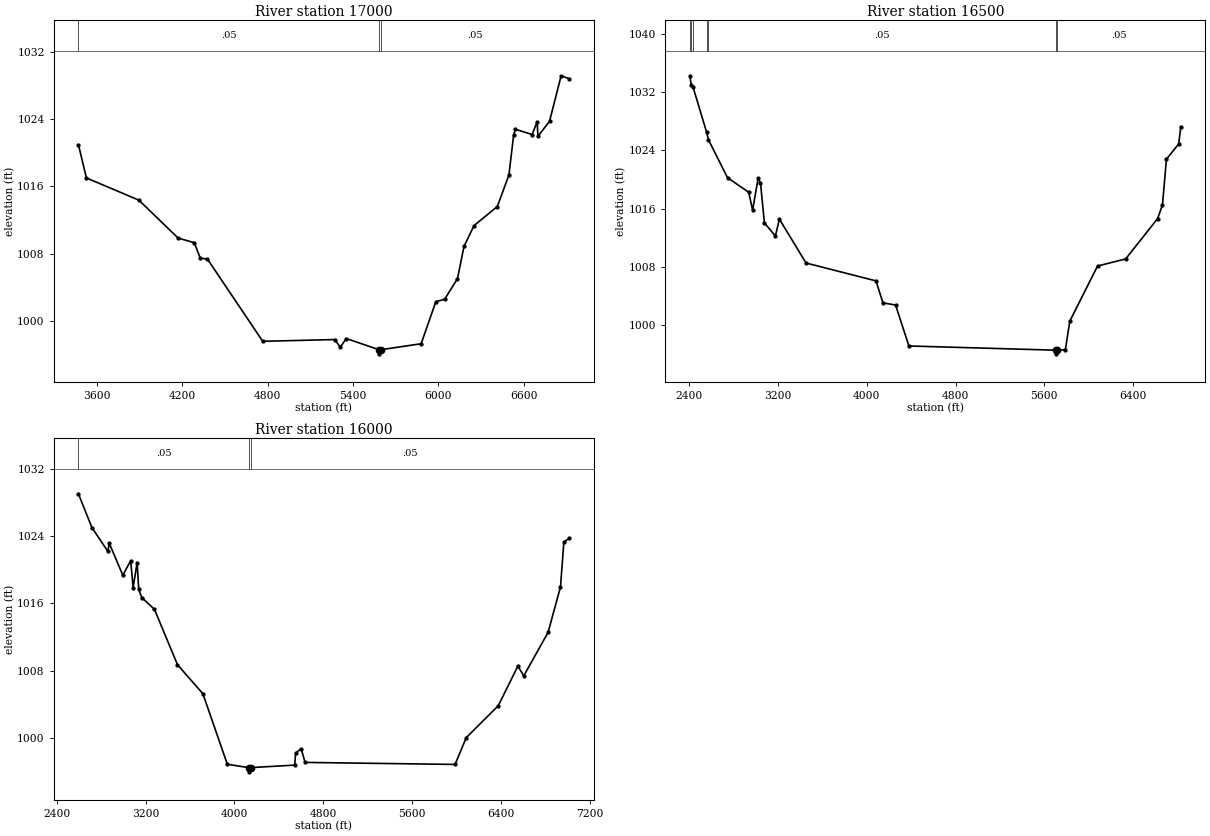
Type RM Length L Ch R = 1 ,17000   ,500,500,500
BEGIN DESCRIPTION:
RED ROCK CREEK 34.0
END DESCRIPTION:
XS GIS Cut Line= 3
      2885605.69     10261603.11      2884466.96     10260580.35
      2882605.67     10260103.11
#Sta/Elev= 30
  3469.4 1020.95  3525.8 1016.99  3894.4 1014.35  4170.2 1009.84  4283.8 1009.29
  4326.4 1007.44  4375.7 1007.36  4765.2  997.56  5269.7  997.77    5311  996.87
  5352.3  997.89  5581.2  996.57  5581.7  996.07  5598.3  996.57  5878.8  997.27
    5982 1002.27    6044 1002.56  6134.1 1005.01    6180 1008.84  6250.5 1011.32
  6414.3 1013.59  6495.9 1017.34  6529.2 1022.11  6541.8 1022.78    6659 1022.15
  6694.4 1023.68  6699.8 1021.93  6781.3 1023.73  6862.9 1029.14  6921.5 1028.78
#Mann= 3 ,-1 , 0
  3469.4     .05       0  5581.2     .03       0  5598.3     .05       0
Bank Sta=5581.2,5598.3
XS Rating Curve= 0 ,0
Exp/Cntr=0.3,0.1

Type RM Length L Ch R = 1 ,16500   ,500,500,500
BEGIN DESCRIPTION:
RED ROCK CREEK 33.0
END DESCRIPTION:
XS GIS Cut Line= 3
      2886505.67      10262053.1      2884734.73      10260158.1
      2882905.66     10260103.11
#Sta/Elev= 30
  2406.3 1034.24  2419.3    1033  2434.3 1032.75  2557.6  1026.5  2574.4 1025.46
    2746 1020.26    2937 1018.26  2972.2  1015.8    3022 1020.19  3043.1 1019.56
  3078.2 1014.07  3177.4 1012.24  3213.1 1014.58  3453.4 1008.55  4083.1  1006.1
  4146.6 1003.08  4259.9 1002.79  4380.1  997.17  5700.8  996.59  5701.3  996.09
  5717.9  996.59  5789.4  996.66  5829.4 1000.58  6079.5 1008.14  6332.7 1009.11
  6619.8 1014.64  6664.1  1016.5  6699.8 1022.79  6809.9 1024.88  6829.9 1027.28
#Mann= 7 ,-1 , 0
  2406.3     .05       0  2419.3     .12       0  2434.3     .05       0
  2557.6     .12       0  2574.4     .05       0  5700.8     .03       0
  5717.9     .05       0
Bank Sta=5700.8,5717.9
XS Rating Curve= 0 ,0
Exp/Cntr=0.3,0.1

Type RM Length L Ch R = 1 ,16000   ,0,0,0
BEGIN DESCRIPTION:
RED ROCK CREEK 32.0
END DESCRIPTION:
XS GIS Cut Line= 3
      2886905.69     10261203.12      2885001.38     10259735.37
      2883005.66     10260003.11
#Sta/Elev= 30
  2595.7    1029  2717.1 1024.99  2860.3 1022.17  2873.5 1023.12  2995.2 1019.33
  3065.9 1021.05  3088.1 1017.87  3123.9 1020.83  3138.4 1017.64  3165.5 1016.68
  3279.7 1015.28  3487.1  1008.7  3715.4 1005.26  3935.5  996.88  4127.5  996.48
    4128  995.98  4144.6  996.48  4541.6  996.78  4549.8  998.21  4599.6  998.73
  4634.9   997.1  5984.4  996.86  6085.3 1000.05  6373.6 1003.84  6549.5 1008.54
  6602.4 1007.38  6821.2 1012.54  6932.9 1017.95  6963.1 1023.27  7013.6 1023.73
#Mann= 3 ,-1 , 0
  2595.7     .05       0  4127.5     .03       0  4144.6     .05       0
Bank Sta=4127.5,4144.6
XS Rating Curve= 0 ,0
Exp/Cntr=0.3,0.1

Chan Stop Cuts=-1
Use User Specified Reach Order=0