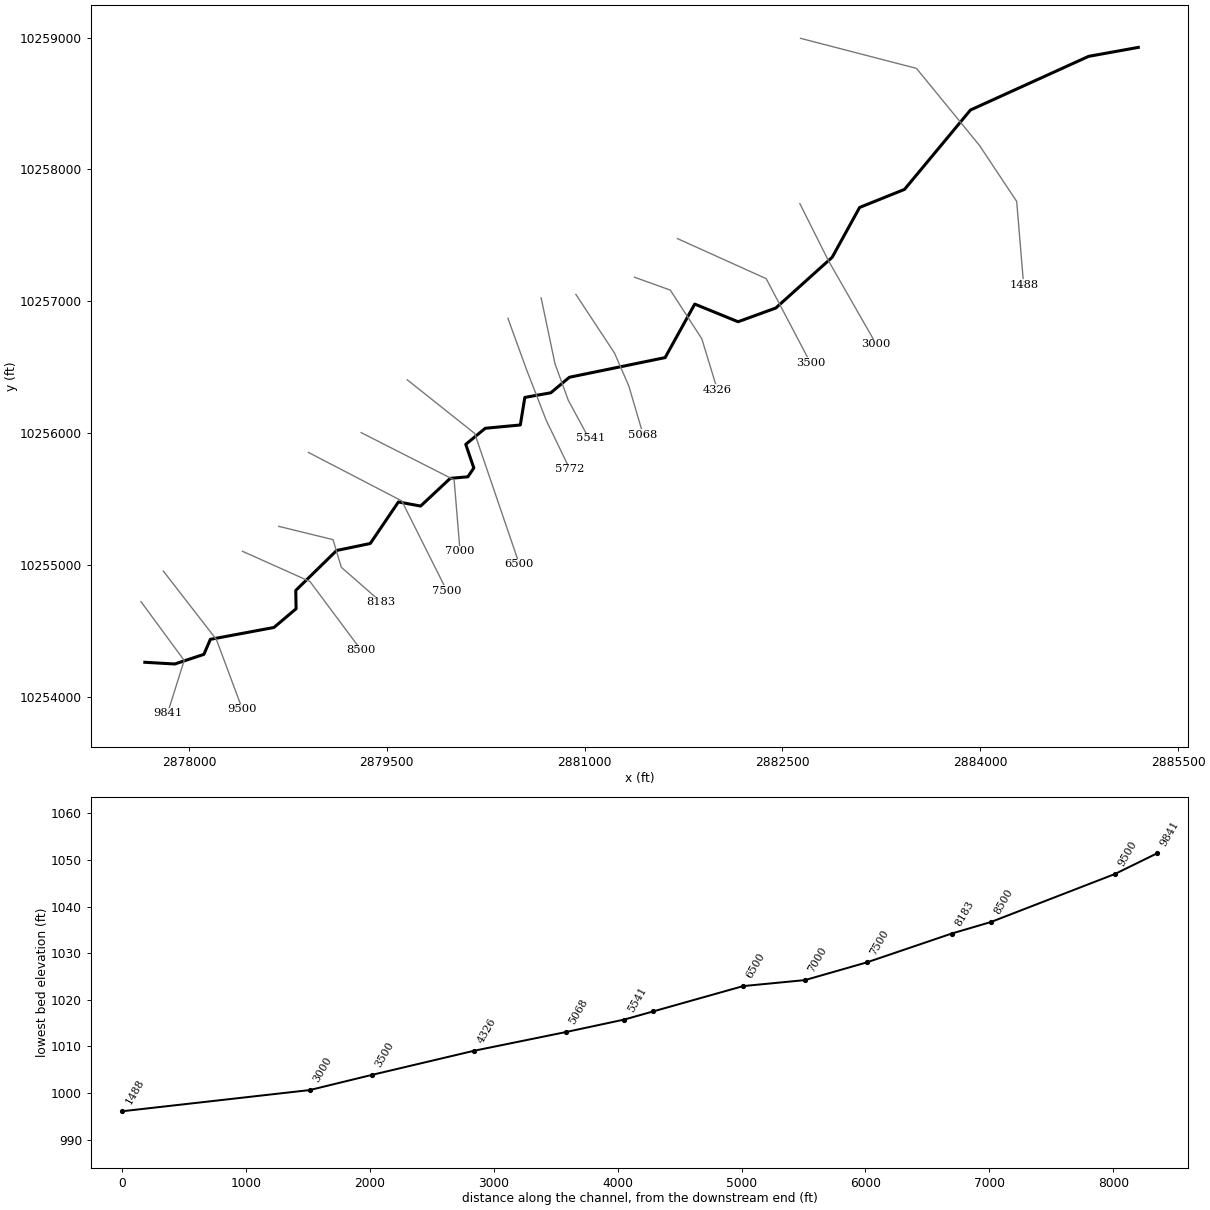
--- SOUTH COGGINS CREEK.prj (project) ---

Proj Title=SOUTH COGGINS CREEK Base Level Engineering
Current Plan=p01
Default Exp/Contr=0.3,0.1
English Units
Geom File=g01
Flow File=f01
Plan File=p01
Y Axis Title=Elevation
X Axis Title(PF)=Main Channel Distance
X Axis Title(XS)=Station
BEGIN DESCRIPTION:
SOUTH COGGINS CREEK
END DESCRIPTION:
DSS Export Rating Curves= 0
DSS Export Rating Curve Sorted= 0
DSS Export Volume Flow Curves= 0
DXF OffsetX= 0
DXF OffsetY= 0
DXF ScaleX= 1
DXF ScaleY= 10

--- SOUTH COGGINS CREEK.p01 (plan) ---

Plan Title=Multiple Run
Short Identifier=Multiple
Geom File=g01
Flow File=f01
Subcritical Flow
K Sum by GR= 0
Std Step Tol= 0.01
Critical Tol= 0.01
Num of Std Step Trials= 20
Max Error Tol= 0.3
Flow Tol Ratio= 0.001
Split Flow NTrial= 30
Split Flow Tol= 0.02
Split Flow Ratio= 0.02
Log Output Level= 0
Friction Slope Method= 1
Unsteady Friction Slope Method= 2
Unsteady Bridges Friction Slope Method= 1
Parabolic Critical Depth
Global Vel Dist=  1 , 1 , 1
Global Log Level= 0
CheckData=True
Encroach Param= -1, 0, 0, 0
BEGIN DESCRIPTION:
Multiple Run
END DESCRIPTION:

--- SOUTH COGGINS CREEK.f01 (steady flow) ---

Flow Title=Multiple
Number of Profiles=7
Profile Names=10-year,25-year,50-year,1pct_min,100-year,1pct_plu,500-year
River Rch & RM= SOUTH COGGINS CR,Reach-1,9841
     444     723     724     500     934    1745    1245
River Rch & RM= SOUTH COGGINS CR,Reach-1,1488
     737    1227    1384     992    1824    3350    2410
Boundary for River Rch & Prof#=SOUTH COGGINS CR,Reach-1,1
Up Type=0
Dn Type=3
Dn Slope=0.005
Boundary for River Rch & Prof#=SOUTH COGGINS CR,Reach-1,2
Up Type=0
Dn Type=3
Dn Slope=0.005
Boundary for River Rch & Prof#=SOUTH COGGINS CR,Reach-1,3
Up Type=0
Dn Type=3
Dn Slope=0.005
Boundary for River Rch & Prof#=SOUTH COGGINS CR,Reach-1,4
Up Type=0
Dn Type=3
Dn Slope=0.005
Boundary for River Rch & Prof#=SOUTH COGGINS CR,Reach-1,5
Up Type=0
Dn Type=3
Dn Slope=0.005
Boundary for River Rch & Prof#=SOUTH COGGINS CR,Reach-1,6
Up Type=0
Dn Type=3
Dn Slope=0.005
Boundary for River Rch & Prof#=SOUTH COGGINS CR,Reach-1,7
Up Type=0
Dn Type=3
Dn Slope=0.005

--- SOUTH COGGINS CREEK.g01 (geometry) ---

Geom Title=Existing Conditions
Program Version=4.00

River Reach=SOUTH COGGINS CR,Reach-1
Reach XY= 30
       2877665.5       10254261.       2877892.5       10254248.
      2878113.25       10254321.       2878162.5       10254435.
       2878644.5       10254525.       2878812.5       10254667.
        2878810.       10254806.      2879119.75       10255109.
        2879375.       10255162.      2879588.25       10255477.
      2879756.75       10255446.      2879981.25       10255656.
      2880115.25       10255668.        2880160.       10255735.
        2880099.       10255914.        2880247.       10256036.
      2880512.75       10256061.        2880547.       10256270.
       2880743.5       10256305.      2880885.25       10256423.
      2881610.75       10256572.      2881835.25       10256978.
      2882163.75       10256844.      2882449.75       10256948.
       2882877.5       10257333.       2883085.5       10257711.
        2883426.       10257848.        2883926.       10258450.
        2884822.       10258857.      2885198.75       10258925.

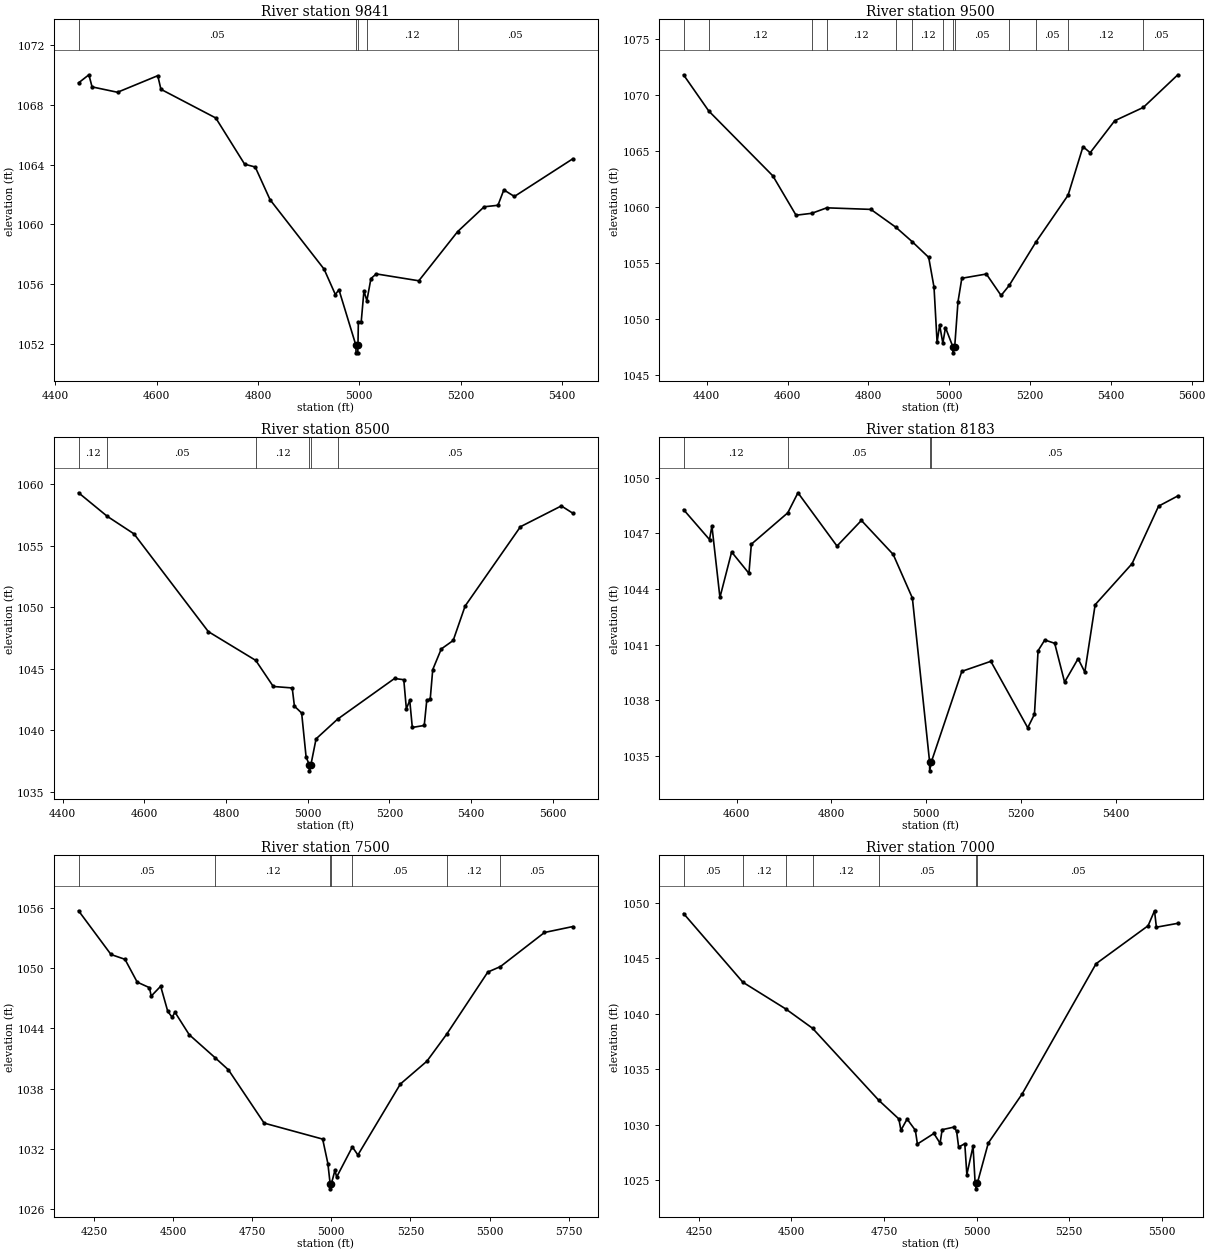
Type RM Length L Ch R = 1 ,9841    ,341,341,341
BEGIN DESCRIPTION:
SOUTH COGGINS CREEK 20.0
END DESCRIPTION:
XS GIS Cut Line= 3
      2877636.13     10254721.19        2877964.       10254275.
      2877837.57     10253873.43
#Sta/Elev= 30
  4446.3 1069.47  4466.7 1070.01  4472.9  1069.2  4523.1 1068.84  4602.5 1069.95
  4608.7 1069.04  4716.9 1067.12  4773.8 1064.03  4794.7 1063.84    4824 1061.65
  4930.5 1057.01  4952.7 1055.31  4959.8 1055.63  4993.3 1051.91  4993.5 1051.41
    4997 1051.41  4997.3 1051.91  4998.1 1053.44  5003.6 1053.44  5009.1 1055.55
  5014.9  1054.9  5022.9 1056.38  5033.4 1056.69  5117.3 1056.23  5193.9 1059.52
  5246.2 1061.18  5273.4 1061.28    5285 1062.31  5305.8 1061.87    5421 1064.39
#Mann= 5 ,-1 , 0
  4446.3     .05       0  4993.3     .05       0  4997.3     .05       0
  5014.9     .12       0  5193.9     .05       0
Bank Sta=4993.3,4997.3
XS Rating Curve= 0 ,0
Exp/Cntr=0.3,0.1

Type RM Length L Ch R = 1 ,9500    ,1000,1000,1000
BEGIN DESCRIPTION:
SOUTH COGGINS CREEK 19.0
END DESCRIPTION:
XS GIS Cut Line= 3
      2877805.71     10254953.08      2878208.33      10254433.4
      2878405.68     10253903.14
#Sta/Elev= 30
  4342.6 1071.83  4404.9  1068.6  4563.5  1062.8  4620.9 1059.28  4659.8 1059.45
    4697 1059.94  4806.1  1059.8  4867.7 1058.21  4908.5 1056.91  4949.2 1055.51
  4962.4 1052.84    4970 1047.91  4976.3 1049.46  4984.2 1047.84  4990.8 1049.23
  5009.5 1047.47  5009.8 1046.97  5013.5 1047.47  5021.7 1051.53  5031.2 1053.64
  5091.9 1054.02  5128.4  1052.1  5148.5    1053  5215.1 1056.91  5294.2 1061.07
  5331.1 1065.41  5348.9 1064.87  5409.6 1067.73  5480.4 1068.92  5565.8 1071.84
#Mann= 13 ,-1 , 0
  4342.6     .05       0  4404.9     .12       0  4659.8     .05       0
    4697     .12       0  4867.7     .05       0  4908.5     .12       0
  4984.2     .05       0  5009.5     .05       0  5013.5     .05       0
  5148.5     .12       0  5215.1     .05       0  5294.2     .12       0
  5480.4     .05       0
Bank Sta=5009.5,5013.5
XS Rating Curve= 0 ,0
Exp/Cntr=0.3,0.1

Type RM Length L Ch R = 1 ,8500    ,317,317,317
BEGIN DESCRIPTION:
SOUTH COGGINS CREEK 17.0
END DESCRIPTION:
XS GIS Cut Line= 3
      2878405.68     10255103.11      2878917.73     10254873.68
      2879305.67     10254353.13
#Sta/Elev= 30
  4438.9 1059.29    4509 1057.38  4574.6 1055.95  4756.7    1048  4872.8 1045.66
  4915.7 1043.54  4962.1 1043.42  4967.5 1041.94  4985.2 1041.38  4996.1  1037.8
  5003.9 1037.18  5004.2 1036.68  5007.9 1037.18  5020.5 1039.28  5073.1 1040.88
  5212.7 1044.19  5235.3 1044.09  5241.6 1041.73  5249.9  1042.4  5256.2 1040.21
  5285.4 1040.37  5291.6 1042.42    5300 1042.49  5306.2 1044.91  5327.1 1046.59
  5356.3 1047.28  5385.5 1050.08    5521 1056.53  5621.1 1058.22  5649.2 1057.63
#Mann= 6 ,-1 , 0
  4438.9     .12       0    4509     .05       0  4872.8     .12       0
  5003.9     .07       0  5007.9     .12       0  5073.1     .05       0
Bank Sta=5003.9,5007.9
XS Rating Curve= 0 ,0
Exp/Cntr=0.3,0.1

Type RM Length L Ch R = 1 ,8183    ,683,683,683
BEGIN DESCRIPTION:
Mapping XS 9a3b99c2
END DESCRIPTION:
XS GIS Cut Line= 4
      2878681.18       10255292.      2879092.46     10255191.27
      2879155.42     10254981.43      2879456.96     10254717.58
#Sta/Elev= 30
  4488.3 1048.27    4543 1046.66  4548.1 1047.39    4565 1043.54  4589.7 1045.99
  4626.2 1044.84  4631.3 1046.41  4708.2  1048.1  4729.7 1049.18  4812.1 1046.31
  4863.6 1047.69  4930.7 1045.86  4971.2 1043.51  5007.5  1034.7  5007.7  1034.2
  5011.5  1034.7  5075.6 1039.56  5136.8  1040.1  5214.7 1036.52  5228.9 1037.25
  5236.5 1040.67  5250.7 1041.25  5271.6 1041.07  5292.5 1038.98    5321 1040.24
  5335.2 1039.52    5357 1043.15  5434.9 1045.36  5490.9 1048.46  5531.5 1049.01
#Mann= 4 ,-1 , 0
  4488.3     .12       0  4708.2     .05       0  5007.5     .05       0
  5011.5     .05       0
Bank Sta=5007.5,5011.5
XS Rating Curve= 0 ,0
Exp/Cntr=0.3,0.1

Type RM Length L Ch R = 1 ,7500    ,500,500,500
BEGIN DESCRIPTION:
SOUTH COGGINS CREEK 15.0
END DESCRIPTION:
XS GIS Cut Line= 3
      2878905.64     10255853.13      2879613.94      10255484.9
      2879955.66     10254803.15
#Sta/Elev= 30
  4201.7  1055.7  4304.1 1051.35  4348.3 1050.87  4386.9  1048.6  4425.5 1048.05
  4431.1 1047.21    4461 1048.19  4483.5 1045.68  4497.4  1045.1  4506.1 1045.61
  4551.1 1043.37  4632.5 1041.09  4675.1 1039.87  4787.8 1034.57  4972.6 1032.98
  4989.1 1030.55  4996.2 1028.53  4996.4 1028.03  5000.2 1028.53  5011.3 1029.87
  5016.9 1029.21  5066.4  1032.2  5083.9  1031.4    5218 1038.46  5301.8 1040.73
  5364.1 1043.41  5494.2  1049.6  5534.2 1050.15  5673.2 1053.54  5762.6 1054.13
#Mann= 7 ,-1 , 0
  4201.7     .05       0  4632.5     .12       0  4996.2     .07       0
  5000.2     .12       0  5066.4     .05       0  5364.1     .12       0
  5534.2     .05       0
Bank Sta=4996.2,5000.2
XS Rating Curve= 0 ,0
Exp/Cntr=0.3,0.1

Type RM Length L Ch R = 1 ,7000    ,500,500,500
BEGIN DESCRIPTION:
SOUTH COGGINS CREEK 14.0
END DESCRIPTION:
XS GIS Cut Line= 3
      2879305.67     10256003.12      2880010.85     10255644.57
      2880055.68     10255103.12
#Sta/Elev= 30
  4208.9 1049.03    4369 1042.84  4484.4 1040.44  4557.1 1038.69  4735.9  1032.2
  4790.1 1030.52  4795.7  1029.5  4812.4 1030.51  4834.6  1029.5  4840.2 1028.26
  4884.7 1029.21  4901.4 1028.33    4907 1029.55  4938.1 1029.78  4945.9 1029.44
  4951.5 1027.98  4968.1 1028.29  4973.7 1025.51  4990.4 1028.06    4996 1024.77
  4997.9 1024.72  4998.2 1024.22  5001.9 1024.72  5031.6 1028.35    5123 1032.77
  5322.6 1044.51    5463 1047.93  5480.4 1049.28  5485.4  1047.8  5543.3 1048.15
#Mann= 7 ,-1 , 0
  4208.9     .05       0    4369     .12       0  4484.4     .05       0
  4557.1     .12       0  4735.9     .05       0  4997.9     .05       0
  5001.9     .05       0
Bank Sta=4997.9,5001.9
XS Rating Curve= 0 ,0
Exp/Cntr=0.3,0.1

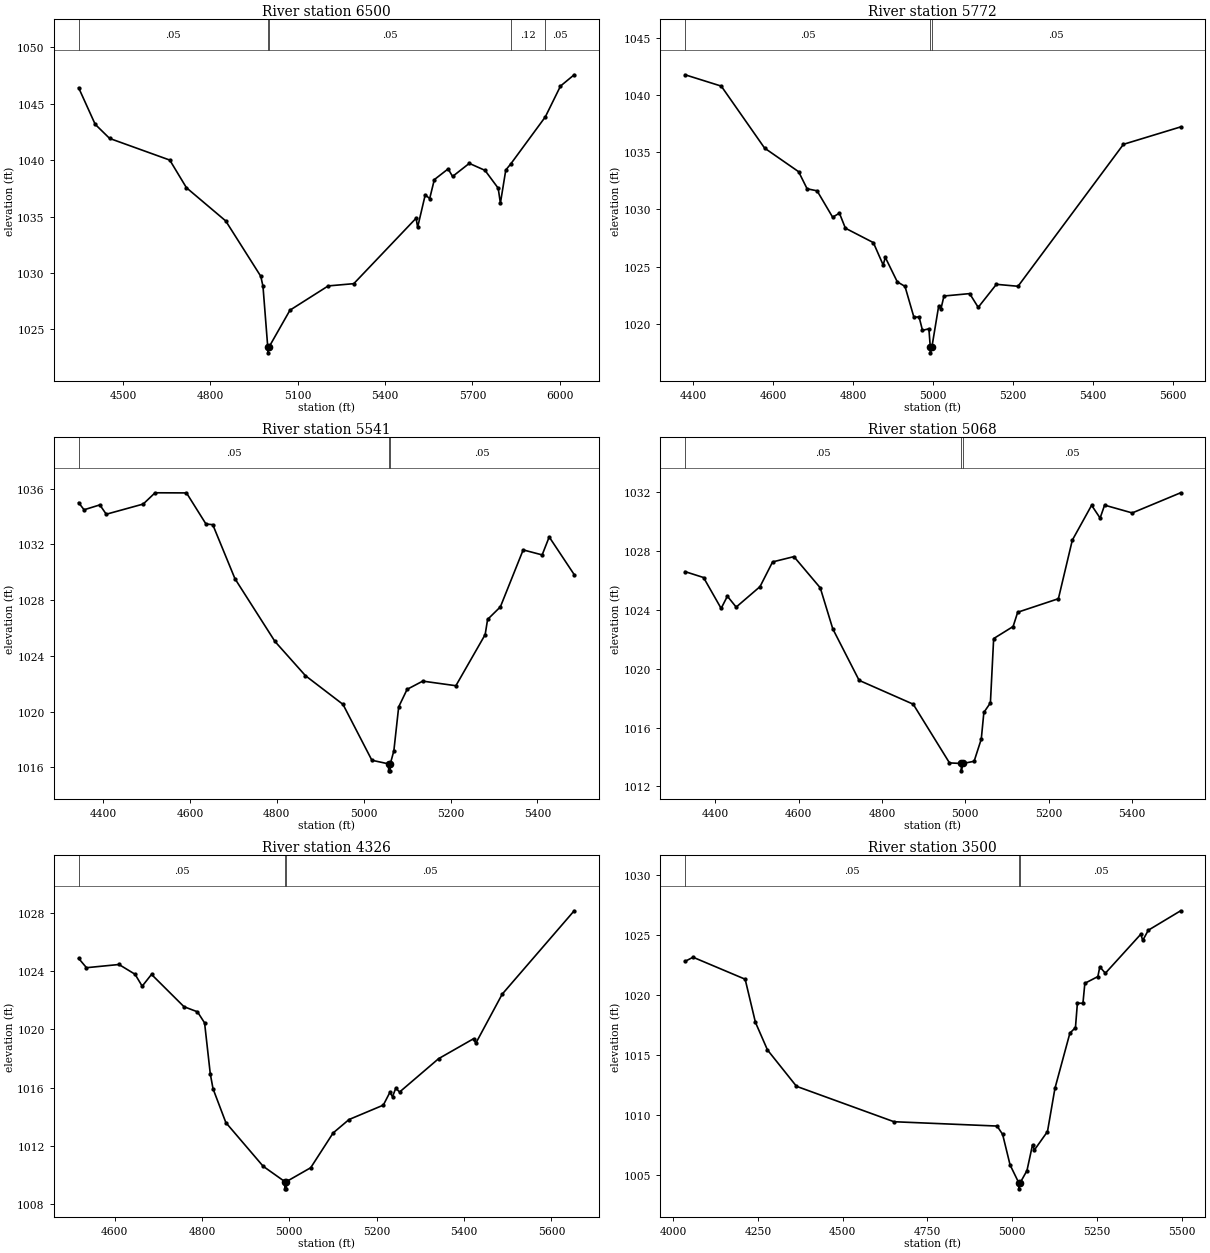
Type RM Length L Ch R = 1 ,6500    ,728,728,728
BEGIN DESCRIPTION:
SOUTH COGGINS CREEK 13.0
END DESCRIPTION:
XS GIS Cut Line= 3
      2879655.68     10256403.11      2880166.91     10255996.67
      2880505.67     10255003.14
#Sta/Elev= 30
  4346.9 1046.42  4403.8 1043.18  4453.4 1041.93  4660.1 1040.01  4717.4 1037.56
  4852.3 1034.62  4972.9 1029.71  4980.4 1028.82  4996.8 1023.43  4997.1 1022.93
  5000.8 1023.43  5073.1 1026.71  5204.5 1028.86  5292.4 1029.06  5506.5 1034.86
  5511.8 1034.06  5537.9 1036.93  5553.2  1036.6  5569.2 1038.28  5616.6 1039.23
  5631.9 1038.56  5689.3 1039.72  5743.3  1039.1  5788.6 1037.52  5796.2 1036.19
  5814.7 1039.13  5832.1 1039.68  5950.6 1043.84  6002.7 1046.57  6049.7 1047.57
#Mann= 5 ,-1 , 0
  4346.9     .05       0  4996.8     .05       0  5000.8     .05       0
  5832.1     .12       0  5950.6     .05       0
Bank Sta=4996.8,5000.8
XS Rating Curve= 0 ,0
Exp/Cntr=0.3,0.1

Type RM Length L Ch R = 1 ,5772    ,231,231,231
BEGIN DESCRIPTION:
Mapping XS 71b9f4f2
END DESCRIPTION:
XS GIS Cut Line= 4
       2880418.7     10256870.07      2880557.21     10256488.14
       2880708.3     10256097.82      2880888.79     10255724.25
#Sta/Elev= 30
    4379 1041.75  4469.5 1040.76  4577.9 1035.35    4663 1033.29  4684.2  1031.8
  4709.2 1031.62  4748.1 1029.32  4765.1 1029.67    4780 1028.36    4850  1027.1
  4874.5 1025.15  4879.9 1025.81  4909.8 1023.68  4929.1 1023.28  4951.5 1020.58
  4964.3 1020.62  4972.9 1019.44  4988.9 1019.58  4992.4 1017.98  4992.6 1017.48
  4996.4 1017.98  5013.5 1021.59  5018.9 1021.29  5026.6 1022.44  5090.9 1022.65
  5112.3 1021.45  5157.8 1023.46  5211.9 1023.29  5475.6 1035.68  5618.7  1037.2
#Mann= 3 ,-1 , 0
    4379     .05       0  4992.4     .03       0  4996.4     .05       0
Bank Sta=4992.4,4996.4
XS Rating Curve= 0 ,0
Exp/Cntr=0.3,0.1

Type RM Length L Ch R = 1 ,5541    ,473,473,473
BEGIN DESCRIPTION:
Mapping XS cb5ea2d8
END DESCRIPTION:
XS GIS Cut Line= 5
      2880670.52     10257025.35      2880775.45     10256525.91
      2880876.18     10256248.91      2881014.68     10255992.89
      2881044.07     10255959.31
#Sta/Elev= 30
  4343.8    1035  4356.3 1034.49  4392.6 1034.84  4407.4 1034.17  4492.4  1034.9
  4519.8 1035.71  4592.1  1035.7  4636.9 1033.47  4652.6 1033.42  4703.7 1029.54
  4795.7 1025.04    4866 1022.58  4952.4 1020.52  5018.9 1016.51  5057.3 1016.25
  5057.5 1015.75    5061 1015.75  5061.3 1016.25  5069.5 1017.19  5080.6 1020.34
    5100  1021.6    5136 1022.19  5212.3 1021.86  5279.7 1025.53  5285.3 1026.62
  5314.7 1027.52  5367.2 1031.61  5410.9 1031.25  5427.1 1032.54  5484.6 1029.84
#Mann= 3 ,-1 , 0
  4343.8     .05       0  5057.3     .03       0  5061.3     .05       0
Bank Sta=5057.3,5061.3
XS Rating Curve= 0 ,0
Exp/Cntr=0.3,0.1

Type RM Length L Ch R = 1 ,5068    ,742,742,742
BEGIN DESCRIPTION:
Mapping XS 76c2c943
END DESCRIPTION:
XS GIS Cut Line= 4
      2880933.89     10257051.47      2881226.88     10256606.57
      2881335.38       10256357.      2881443.89     10255988.07
#Sta/Elev= 30
  4327.4  1026.6  4371.7  1026.2  4413.9  1024.1  4428.9 1024.93    4450 1024.19
  4507.2 1025.58  4537.4 1027.26  4588.6 1027.62  4651.8  1025.5  4681.9 1022.71
  4745.1 1019.21  4874.9 1017.59    4962  1013.6  4990.2 1013.56  4990.4 1013.06
  4994.2 1013.56  5021.1 1013.71  5038.3 1015.22  5044.5 1017.03  5060.2 1017.68
    5068 1022.05  5114.7 1022.87  5125.7 1023.84  5223.4 1024.76  5256.8 1028.74
  5303.1 1031.11  5323.5 1030.24  5334.3 1031.12  5400.6 1030.59  5516.8 1031.96
#Mann= 3 ,-1 , 0
  4327.4     .05       0  4990.2     .03       0  4994.2     .05       0
Bank Sta=4990.2,4994.2
XS Rating Curve= 0 ,0
Exp/Cntr=0.5,0.3

Type RM Length L Ch R = 1 ,4326    ,826,826,826
BEGIN DESCRIPTION:
Mapping XS 255d5cd5
END DESCRIPTION:
XS GIS Cut Line= 4
      2881378.77     10257181.66      2881650.05       10257084.
      2881888.77     10256715.08      2882007.57     10256326.27
#Sta/Elev= 30
  4517.7 1024.87  4535.7 1024.23  4610.1 1024.45  4646.8 1023.78  4663.2 1022.96
  4684.5 1023.77  4758.9 1021.55  4789.7  1021.2    4806 1020.44    4819 1016.95
  4825.3 1015.92  4854.7 1013.59  4940.1 1010.59  4989.5 1009.54  4989.7 1009.04
  4993.2 1009.04  4993.5 1009.54  5048.9 1010.49  5100.3 1012.88  5136.6  1013.8
  5215.1 1014.79  5230.2 1015.67  5236.2 1015.37  5243.6 1015.95  5252.4 1015.69
  5341.6 1017.98  5421.6 1019.35  5426.8 1019.04  5487.2 1022.41    5652 1028.14
#Mann= 3 ,-1 , 0
  4517.7     .05       0  4989.5     .03       0  4993.5     .05       0
Bank Sta=4989.5,4993.5
XS Rating Curve= 0 ,0
Exp/Cntr=0.5,0.3

Type RM Length L Ch R = 1 ,3500    ,500,500,500
BEGIN DESCRIPTION:
Mapping XS 32de0198
END DESCRIPTION:
XS GIS Cut Line= 3
      2881704.27     10257474.64      2882377.05     10257170.81
      2882713.43      10256530.6
#Sta/Elev= 30
  4035.2  1022.8  4058.7 1023.14  4212.3 1021.31  4242.6 1017.72  4278.1 1015.42
  4363.7 1012.39  4651.2 1009.44  4955.2 1009.08  4971.6 1008.39  4993.6 1005.84
  5019.3 1004.35  5019.6 1003.85  5023.3 1004.35  5043.4 1005.37  5059.8 1007.52
  5065.4 1007.09  5103.9 1008.62  5125.9 1012.22    5170 1016.82  5186.4 1017.28
  5192.1 1019.31  5208.5 1019.31  5214.1 1020.97  5252.5 1021.53  5258.2 1022.34
  5274.6 1021.81  5379.2 1025.06  5384.8 1024.54  5401.2 1025.39  5496.6 1027.01
#Mann= 3 ,-1 , 0
  4035.2     .05       0  5019.3     .03       0  5023.3     .05       0
#XS Ineff= 2 , 0
       0    4955          5059.8       0
Permanent Ineff=
       F       F
Bank Sta=5019.3,5023.3
XS Rating Curve= 0 ,0
Exp/Cntr=0.5,0.3

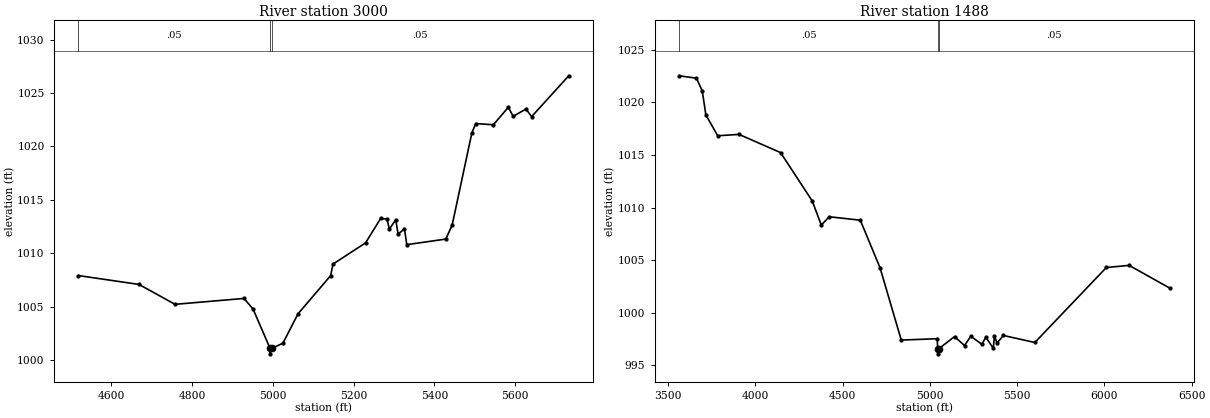
Type RM Length L Ch R = 1 ,3000    ,1512,1512,1512
BEGIN DESCRIPTION:
SOUTH COGGINS CREEK 6.0
END DESCRIPTION:
XS GIS Cut Line= 3
      2882632.36     10257739.83      2882848.05     10257309.12
      2883211.61     10256673.33
#Sta/Elev= 30
  4518.3 1007.93  4668.3  1007.1  4757.7 1005.24  4928.4 1005.79  4950.8  1004.8
    4993 1001.11  4993.2 1000.61    4997 1001.11  5024.8 1001.61  5062.3 1004.36
  5142.9 1007.92  5148.6    1009  5229.2 1010.98  5266.7 1013.27  5282.5 1013.21
  5288.2 1012.26  5304.1 1013.16  5309.8 1011.81  5325.7 1012.29  5331.4 1010.82
  5427.9 1011.34  5443.7 1012.64  5492.6 1021.28  5502.3 1022.14  5545.9 1022.03
  5582.9 1023.67  5594.8 1022.82  5626.5  1023.5  5640.5 1022.79  5732.4 1026.61
#Mann= 3 ,-1 , 0
  4518.3     .05       0    4993     .03       0    4997     .05       0
#XS Ineff= 2 , 0
       0  4986.8            5009       0
Permanent Ineff=
       F       F
Bank Sta=4993,4997
XS Rating Curve= 0 ,0
Exp/Cntr=0.3,0.1

Type RM Length L Ch R = 1 ,1488    ,0,0,0
BEGIN DESCRIPTION:
SOUTH COGGINS CREEK 5.0
END DESCRIPTION:
XS GIS Cut Line= 5
       2882637.5     10258993.71      2883516.37     10258765.86
      2883994.22     10258181.56      2884276.53     10257756.61
      2884329.36     10257122.63
#Sta/Elev= 30
    3564 1022.54  3663.1 1022.31  3696.4  1021.1  3717.1 1018.81  3784.9 1016.83
  3906.7 1016.96    4145 1015.23  4326.6 1010.62  4378.2 1008.33  4423.9 1009.12
  4601.7 1008.79  4715.1 1004.25  4836.4  997.38  5042.4  997.51  5045.2  996.57
  5045.7  996.07  5052.5  996.57  5141.5  997.71  5198.9  996.86  5234.7  997.75
  5297.8  996.98  5320.9  997.65  5363.9  996.59  5369.9  997.78    5385  997.09
  5421.1  997.82  5601.5  997.15  6011.4 1004.29  6141.8 1004.49  6373.1 1002.34
#Mann= 3 ,-1 , 0
    3564     .05       0  5045.2     .03       0  5052.5     .05       0
Bank Sta=5045.2,5052.5
XS Rating Curve= 0 ,0
Exp/Cntr=0.3,0.1

Chan Stop Cuts=-1
Use User Specified Reach Order=0