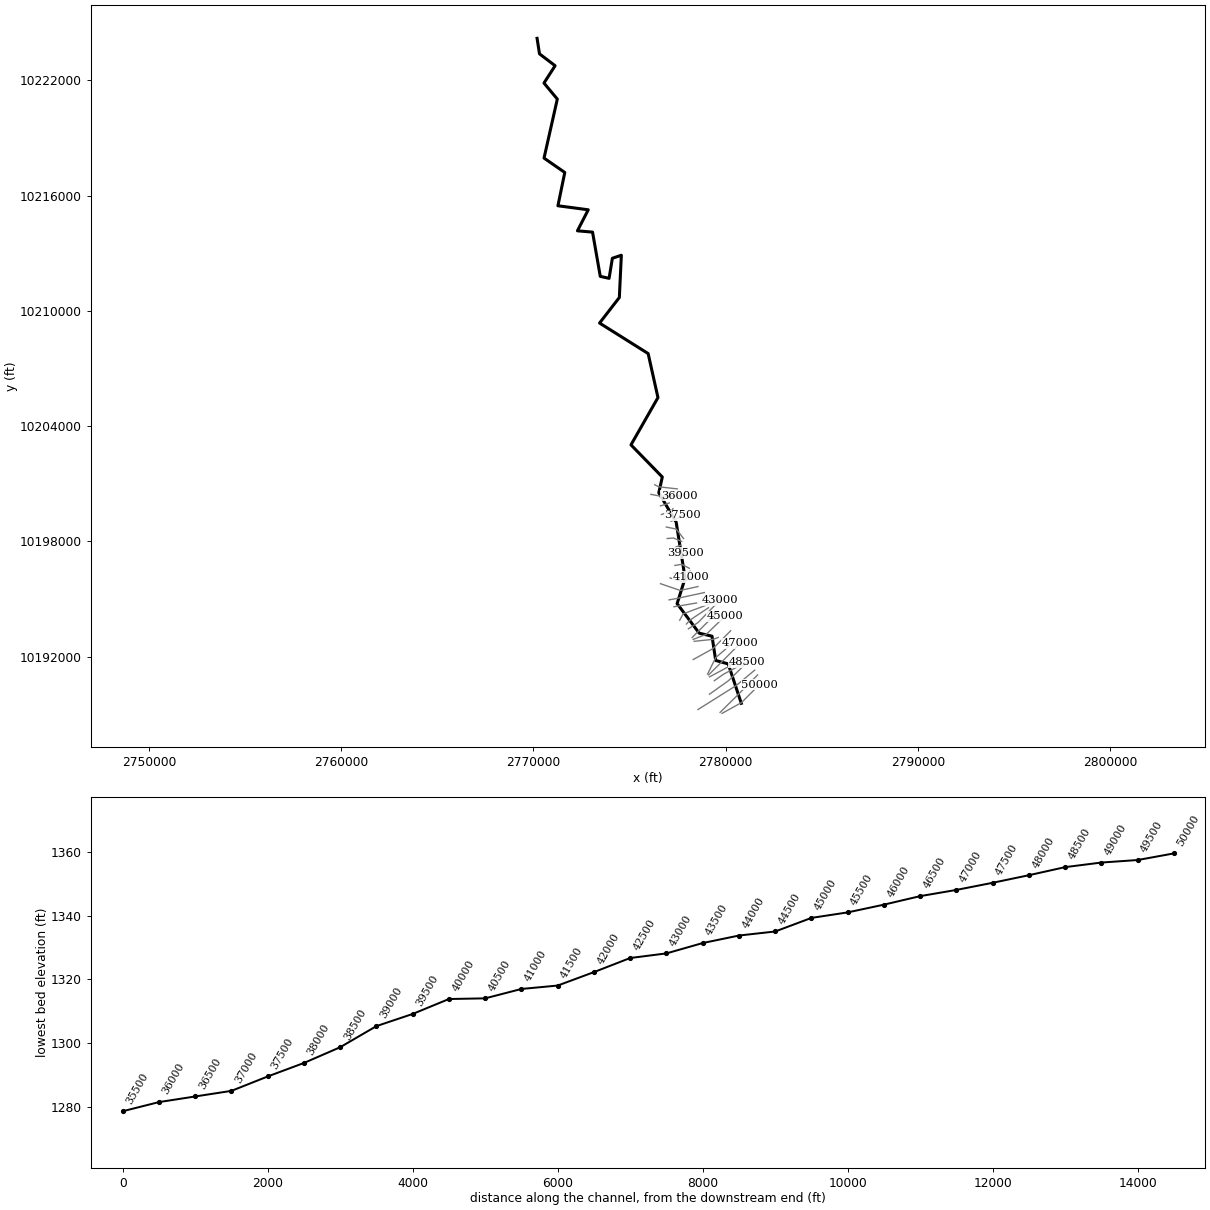
--- BENNETT CREEK.prj (project) ---

Proj Title=BENNETT CREEK Base Level Engineering
Current Plan=p01
Default Exp/Contr=0.3,0.1
English Units
Geom File=g01
Flow File=f01
Plan File=p01
Y Axis Title=Elevation
X Axis Title(PF)=Main Channel Distance
X Axis Title(XS)=Station
BEGIN DESCRIPTION:
BENNETT CREEK
END DESCRIPTION:
DSS Export Rating Curves= 0
DSS Export Rating Curve Sorted= 0
DSS Export Volume Flow Curves= 0
DXF OffsetX= 0
DXF OffsetY= 0
DXF ScaleX= 1
DXF ScaleY= 10

--- BENNETT CREEK.p01 (plan) ---

Plan Title=Multiple Run
Short Identifier=Multiple
Geom File=g01
Flow File=f01
Subcritical Flow
K Sum by GR= 0
Std Step Tol= 0.01
Critical Tol= 0.01
Num of Std Step Trials= 20
Max Error Tol= 0.3
Flow Tol Ratio= 0.001
Split Flow NTrial= 30
Split Flow Tol= 0.02
Split Flow Ratio= 0.02
Log Output Level= 0
Friction Slope Method= 1
Unsteady Friction Slope Method= 2
Unsteady Bridges Friction Slope Method= 1
Parabolic Critical Depth
Global Vel Dist=  1 , 1 , 1
Global Log Level= 0
CheckData=True
Encroach Param= -1, 0, 0, 0
BEGIN DESCRIPTION:
Multiple Run
END DESCRIPTION:

--- BENNETT CREEK.f01 (steady flow) ---

Flow Title=Multiple
Program Version=4.10
Number of Profiles= 7
Profile Names=10-year,25-year,50-year,1pct_min,100-year,1pct_plu,500-year
River Rch & RM=BENNETT CREEK,Reach-1         ,50000
     754    1267    1317     890    1730    3363    2292
River Rch & RM=BENNETT CREEK,Reach-1         ,40500
     924    1574    1753    1185    2334    4599    3107
River Rch & RM=BENNETT CREEK,Reach-1         ,38000
    1395    2435    2971    1999    4040    8164    5392
River Rch & RM=BENNETT CREEK,Reach-1         ,32219
    1559    2744    3378    2249    4617    9479    6169
River Rch & RM=BENNETT CREEK,Reach-1         ,29000
    1697    2999    3808    2548    5230   10735    6994
River Rch & RM=BENNETT CREEK,Reach-1         ,28000
    1900    3392    4331    2847    5985   12579    8028
River Rch & RM=BENNETT CREEK,Reach-1         ,23500
    2056    3687    4761    3127    6599   13928    8848
River Rch & RM=BENNETT CREEK,Reach-1         ,21500
    2442    4448    5675    3620    7919   17324   10642
River Rch & RM=BENNETT CREEK,Reach-1         ,12500
    2664    4887    6429    4073    9039   20058   12211
River Rch & RM=BENNETT CREEK,Reach-1         ,7500
    3149    5881    8318    5321   11842   26358   15949
River Rch & RM=BENNETT CREEK,Reach-1         ,2500
    3235    6059    8538    5433   12164   27236   16375
Boundary for River Rch & Prof#=BENNETT CREEK,Reach-1         , 1
Up Type= 0
Dn Type= 3
Dn Slope=0.0005
Boundary for River Rch & Prof#=BENNETT CREEK,Reach-1         , 2
Up Type= 0
Dn Type= 3
Dn Slope=0.0005
Boundary for River Rch & Prof#=BENNETT CREEK,Reach-1         , 3
Up Type= 0
Dn Type= 3
Dn Slope=0.0005
Boundary for River Rch & Prof#=BENNETT CREEK,Reach-1         , 4
Up Type= 0
Dn Type= 3
Dn Slope=0.0005
Boundary for River Rch & Prof#=BENNETT CREEK,Reach-1         , 5
Up Type= 0
Dn Type= 3
Dn Slope=0.0005
Boundary for River Rch & Prof#=BENNETT CREEK,Reach-1         , 6
Up Type= 0
Dn Type= 3
Dn Slope=0.0005
Boundary for River Rch & Prof#=BENNETT CREEK,Reach-1         , 7
Up Type= 0
Dn Type= 3
Dn Slope=0.0005
DSS Import GetInterval= 0
DSS Import GetPeak= 0
DSS Import FillOption= 0

--- BENNETT CREEK.g01 (geometry) ---

Geom Title=Existing Conditions

River Reach=BENNETT CREEK,Reach-1
Reach XY= 30
      2780808.75     10189577.00      2780128.00     10191627.00
      2779477.25     10191807.00      2779285.75     10193070.00
      2778621.00     10193226.00      2777469.75     10194765.00
      2777885.75     10196084.00      2777421.00     10199007.00
      2776517.25     10200534.00      2776700.25     10201355.00
      2775071.00     10203028.00      2776474.25     10205488.00
      2775963.75     10207780.00      2773436.75     10209368.00
      2774466.00     10210697.00      2774570.00     10212897.00
      2774103.50     10212740.00      2773932.50     10211695.00
      2773474.25     10211797.00      2773072.25     10214101.00
      2772286.75     10214168.00      2772849.25     10215263.00
      2771272.00     10215472.00      2771628.25     10217205.00
      2770549.25     10217953.00      2771240.00     10221025.00
      2770546.25     10221858.00      2771125.25     10222761.00
      2770313.00     10223379.00      2770187.25     10224186.00

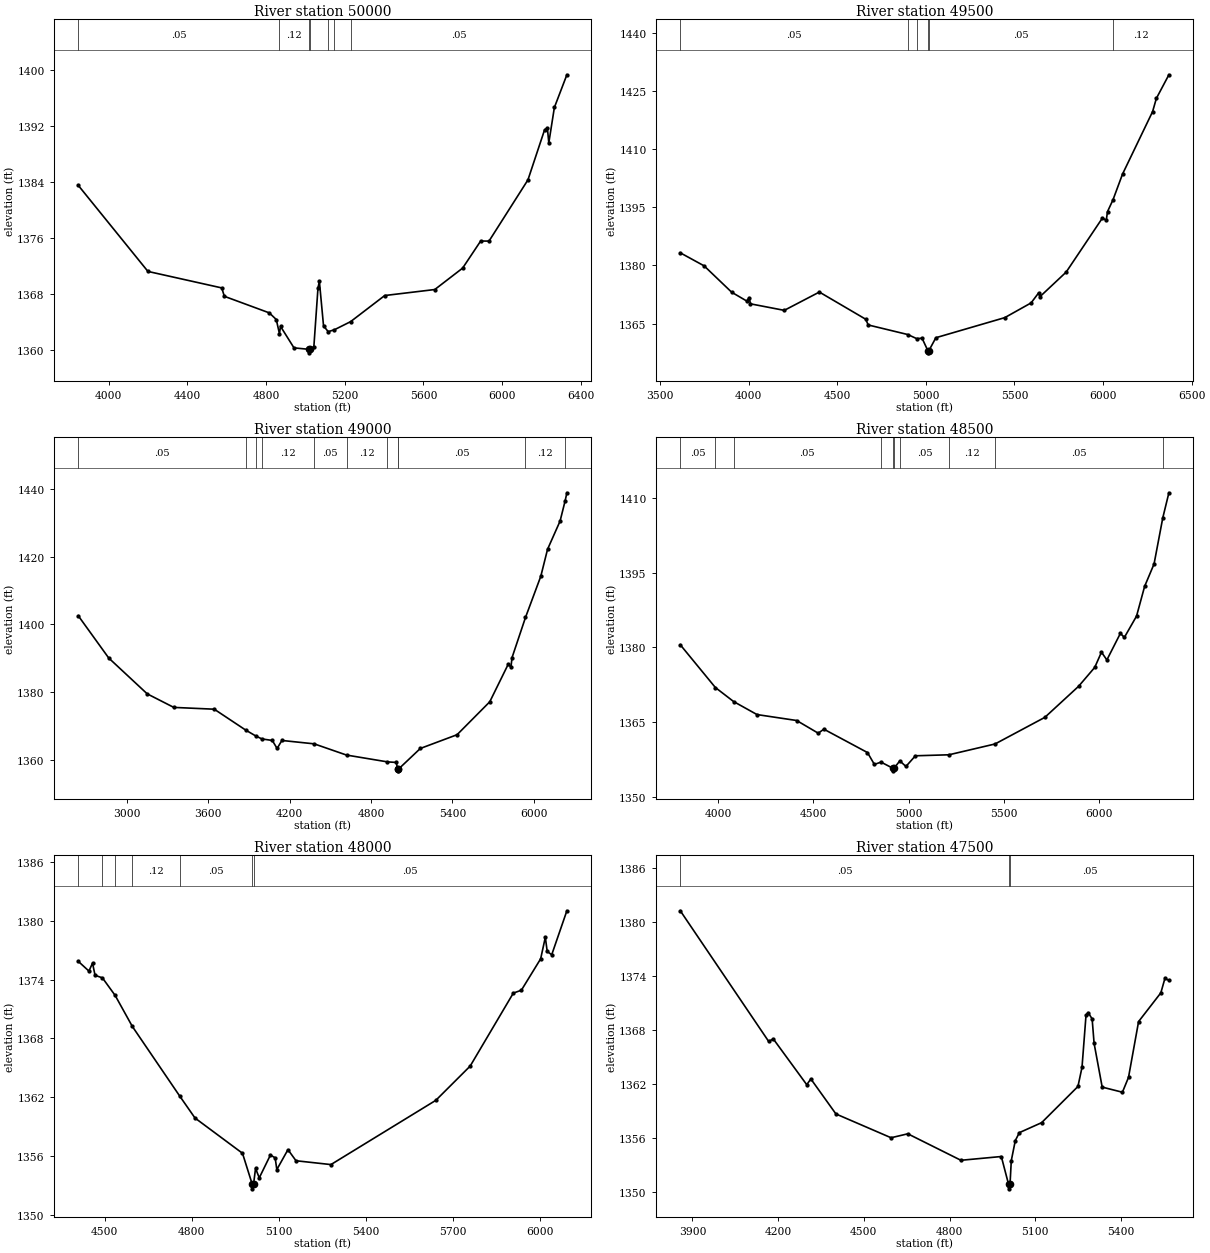
Type RM Length L Ch R = 1,50000,500,500,500
BEGIN DESCRIPTION:
BENNETT CREEK 100.0
END DESCRIPTION:
XS GIS Cut Line= 3
      2779805.71     10189053.12      2780816.78     10189612.09
      2781755.68     10190553.11
#Sta/Elev= 30
  3844.7 1383.50  4198.9 1371.19  4574.3 1368.83  4587.4 1367.63  4815.9 1365.26
  4851.5 1364.31  4867.6 1362.29  4873.3 1363.32  4941.6 1360.25  5019.0 1360.04
  5019.3 1359.54  5023.4 1360.04  5042.4 1360.32  5063.6 1368.82  5070.7 1369.78
  5091.9 1363.38  5115.9 1362.57  5147.5 1362.85  5229.3 1364.00  5403.0 1367.74
  5657.6 1368.60  5799.0 1371.66  5890.9 1375.54  5933.3 1375.53  6131.3 1384.29
  6216.2 1391.48  6230.3 1391.66  6237.4 1389.59  6265.7 1394.65  6329.3 1399.33
#Mann=7,-1,0
  3844.7    0.05       0  4867.6    0.12       0  5019.0    0.07       0
  5023.4    0.12       0  5115.9    0.05       0  5147.5    0.12       0
  5229.3    0.05       0
Bank Sta=5019,5023.4
Exp/Cntr=0.3,0.1

Type RM Length L Ch R = 1,49500,500,500,500
BEGIN DESCRIPTION:
BENNETT CREEK 99.0
END DESCRIPTION:
XS GIS Cut Line= 3
      2779705.67     10189103.10      2780691.02     10190078.25
      2781655.70     10191053.13
#Sta/Elev= 30
  3613.7 1383.26  3748.1 1379.90  3903.6 1373.10  3988.5 1370.83  4002.6 1371.70
  4009.7 1370.10  4200.6 1368.42  4398.6 1373.14  4660.2 1366.13  4674.4 1364.65
  4897.8 1362.18  4947.2 1361.14  4978.4 1361.23  5011.5 1357.96  5011.8 1357.46
  5016.1 1357.96  5056.2 1361.36  5445.1 1366.54  5593.7 1370.34  5636.1 1372.91
  5643.1 1371.92  5791.7 1378.29  5996.7 1392.27  6017.9 1391.63  6025.0 1393.89
  6056.0 1396.94  6109.8 1403.57  6279.5 1419.69  6300.8 1423.10  6371.5 1429.19
#Mann=6,-1,0
  3613.7    0.05       0  4897.8    0.12       0  4947.2    0.05       0
  5011.5    0.05       0  5016.1    0.05       0  6056.0    0.12       0
Bank Sta=5011.5,5016.1
Exp/Cntr=0.3,0.1

Type RM Length L Ch R = 1,49000,500,500,500
BEGIN DESCRIPTION:
BENNETT CREEK 98.0
END DESCRIPTION:
XS GIS Cut Line= 3
      2778555.67     10189253.10      2780550.62     10190507.21
      2781505.66     10191303.10
#Sta/Elev= 30
  2643.6 1402.55  2868.0 1390.05  3151.5 1379.45  3347.3 1375.44  3645.3 1374.91
  3876.2 1368.75  3950.6 1367.00  3996.4 1366.11  4072.9 1365.66  4108.3 1363.29
  4143.7 1365.66  4381.2 1364.66  4619.6 1361.34  4921.3 1359.32  4985.6 1359.16
  4997.6 1357.17  4998.0 1356.67  5002.3 1357.17  5163.5 1363.29  5434.2 1367.36
  5675.0 1377.10  5810.4 1388.16  5831.2 1387.39  5839.0 1390.16  5938.3 1402.06
  6051.2 1414.26  6100.7 1422.22  6193.1 1430.58  6230.5 1436.59  6243.2 1438.95
#Mann=11,-1,0
  2643.6    0.05       0  3876.2    0.12       0  3950.6    0.05       0
  3996.4    0.12       0  4381.2    0.05       0  4619.6    0.12       0
  4921.3    0.05       0  4997.6    0.05       0  5002.3    0.05       0
  5938.3    0.12       0  6230.5    0.05       0
Bank Sta=4997.6,5002.3
Exp/Cntr=0.3,0.1

Type RM Length L Ch R = 1,48500,500,500,500
BEGIN DESCRIPTION:
BENNETT CREEK 97.0
END DESCRIPTION:
XS GIS Cut Line= 3
      2779155.65     10190053.08      2780132.43     10190746.53
      2781105.72     10191703.14
#Sta/Elev= 30
  3802.1 1380.52  3986.0 1371.95  4081.8 1369.13  4204.4 1366.52  4412.3 1365.33
  4525.7 1362.78  4555.0 1363.59  4783.8 1358.90  4820.0 1356.52  4854.9 1356.98
  4918.0 1355.73  4918.3 1355.23  4922.7 1355.73  4953.4 1357.23  4985.5 1356.11
  5035.2 1358.25  5211.1 1358.45  5452.9 1360.62  5714.1 1365.96  5890.8 1372.18
  5975.7 1375.98  6011.1 1379.04  6039.4 1377.48  6110.1 1382.80  6131.3 1382.01
  6195.0 1386.27  6237.4 1392.24  6286.9 1396.74  6332.7 1406.00  6364.7 1411.02
#Mann=10,-1,0
  3802.1    0.05       0  3986.0    0.12       0  4081.8    0.05       0
  4854.9    0.12       0  4918.0    0.05       0  4922.7    0.12       0
  4953.4    0.05       0  5211.1    0.12       0  5452.9    0.05       0
  6332.7    0.12       0
Bank Sta=4918,4922.7
Exp/Cntr=0.3,0.1

Type RM Length L Ch R = 1,48000,500,500,500
BEGIN DESCRIPTION:
BENNETT CREEK 96.0
END DESCRIPTION:
XS GIS Cut Line= 3
      2779405.72     10190753.14      2779888.02     10191094.88
      2780855.68     10191603.11
#Sta/Elev= 30
  4408.9 1375.85  4445.6 1374.86  4458.0 1375.67  4466.7 1374.43  4492.1 1374.17
  4536.0 1372.38  4595.3 1369.22  4757.9 1362.16  4811.2 1359.90  4974.9 1356.31
  5008.1 1353.19  5008.5 1352.69  5013.1 1353.19  5019.9 1354.77  5032.7 1353.81
  5071.1 1356.13  5087.5 1355.85  5093.2 1354.65  5131.6 1356.68  5159.3 1355.55
  5279.7 1355.16  5641.2 1361.70  5759.7 1365.19  5908.4 1372.62  5936.1 1372.91
  6002.6 1376.11  6018.7 1378.30  6025.2 1376.86  6040.7 1376.52  6093.0 1381.00
#Mann=7,-1,0
  4408.9    0.05       0  4492.1    0.12       0  4536.0    0.05       0
  4595.3    0.12       0  4757.9    0.05       0  5008.1    0.05       0
  5013.1    0.05       0
Bank Sta=5008.1,5013.1
Exp/Cntr=0.3,0.1

Type RM Length L Ch R = 1,47500,500,500,500
BEGIN DESCRIPTION:
BENNETT CREEK 95.0
END DESCRIPTION:
XS GIS Cut Line= 3
      2779155.73     10190953.13      2780162.25     10191493.71
      2780555.68     10191903.11
#Sta/Elev= 30
  3857.5 1381.28  4166.8 1366.73  4183.0 1367.01  4300.1 1361.91  4314.5 1362.55
  4402.3 1358.65  4595.3 1356.00  4653.9 1356.44  4839.8 1353.49  4981.2 1353.91
  5006.6 1350.81  5007.0 1350.31  5011.7 1350.81  5016.1 1353.45  5030.2 1355.69
  5044.4 1356.57  5122.3 1357.68  5249.4 1361.71  5263.6 1363.83  5277.7 1369.65
  5284.9 1369.95  5299.1 1369.24  5306.0 1366.51  5334.3 1361.64  5405.1 1361.07
  5426.4 1362.72  5461.7 1368.94  5539.6 1372.14  5553.8 1373.74  5567.8 1373.54
#Mann=3,-1,0
  3857.5    0.05       0  5006.6    0.05       0  5011.7    0.05       0
Bank Sta=5006.6,5011.7
Exp/Cntr=0.3,0.1

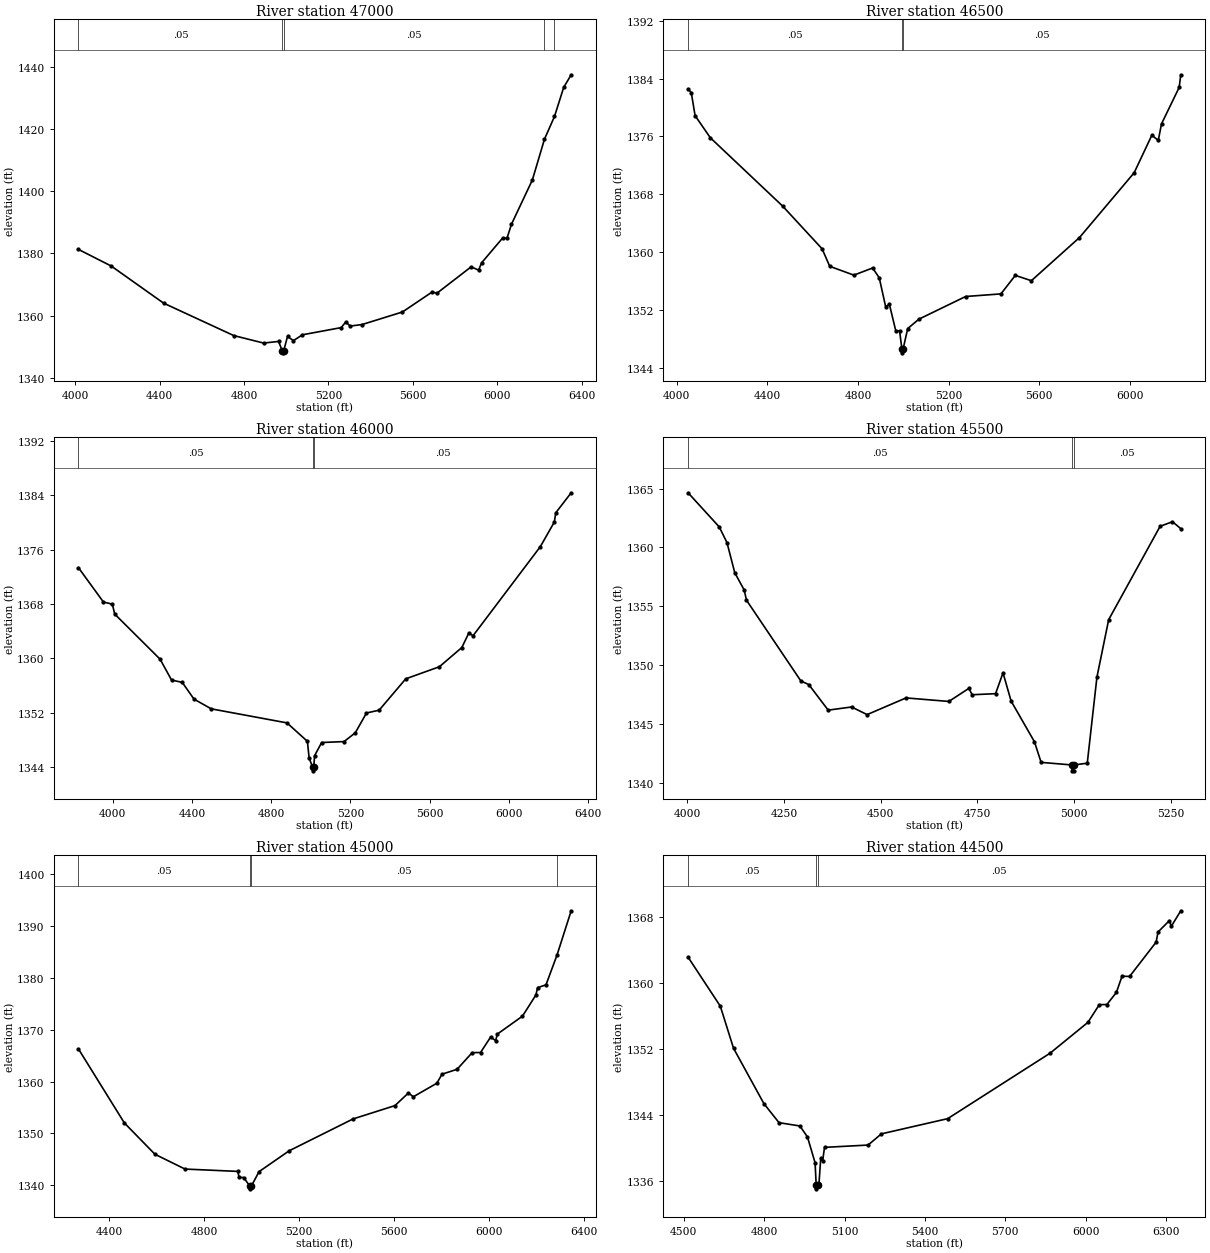
Type RM Length L Ch R = 1,47000,500,500,500
BEGIN DESCRIPTION:
BENNETT CREEK 94.0
END DESCRIPTION:
XS GIS Cut Line= 3
      2779105.71     10191053.14      2779804.48     10191745.53
      2780755.66     10192703.09
#Sta/Elev= 30
  4016.3 1381.30  4171.8 1375.94  4419.3 1364.04  4751.6 1353.62  4893.1 1351.21
  4963.8 1351.73  4982.5 1348.57  4982.9 1348.07  4987.6 1348.57  5006.2 1353.32
  5034.5 1352.00  5076.9 1353.87  5260.8 1356.18  5282.0 1357.99  5303.2 1356.67
  5359.8 1357.17  5550.7 1361.20  5692.1 1367.66  5713.3 1367.19  5876.0 1375.71
  5911.3 1374.64  5925.5 1377.00  6024.5 1384.91  6045.7 1384.89  6066.9 1389.39
  6165.9 1403.62  6223.3 1416.73  6270.7 1424.02  6314.4 1433.38  6349.7 1437.41
#Mann=5,-1,0
  4016.3    0.05       0  4982.5    0.05       0  4987.6    0.05       0
  6223.3    0.12       0  6270.7    0.05       0
Bank Sta=4982.5,4987.6
Exp/Cntr=0.3,0.1

Type RM Length L Ch R = 1,46500,500,500,500
BEGIN DESCRIPTION:
BENNETT CREEK 93.0
END DESCRIPTION:
XS GIS Cut Line= 3
      2779055.67     10191103.08      2779477.07     10191954.39
      2780405.72     10192753.14
#Sta/Elev= 30
  4050.1 1382.55  4064.1 1382.07  4081.0 1378.88  4148.3 1375.82  4467.9 1366.37
  4641.5 1360.49  4675.3 1358.07  4781.9 1356.85  4864.7 1357.84  4894.0 1356.47
  4922.0 1352.51  4938.9 1352.80  4966.9 1349.15  4983.7 1349.16  4993.9 1346.62
  4994.3 1346.12  4999.0 1346.62  5019.5 1349.47  5068.9 1350.77  5275.2 1353.90
  5431.0 1354.26  5494.6 1356.82  5565.3 1356.08  5777.7 1362.04  6019.1 1370.99
  6097.0 1376.16  6125.6 1375.47  6139.8 1377.74  6217.7 1382.77  6224.9 1384.52
#Mann=3,-1,0
  4050.1    0.05       0  4993.9    0.05       0  4999.0    0.05       0
Bank Sta=4993.9,4999
Exp/Cntr=0.3,0.1

Type RM Length L Ch R = 1,46000,500,500,500
BEGIN DESCRIPTION:
BENNETT CREEK 92.0
END DESCRIPTION:
XS GIS Cut Line= 3
      2778305.66     10191853.10      2779330.67     10192420.98
      2780255.67     10193353.10
#Sta/Elev= 30
  3828.2 1373.35  3954.0 1368.30  3998.8 1367.99  4011.1 1366.52  4239.8 1359.88
  4297.6 1356.81  4351.4 1356.47  4410.9 1354.00  4497.9 1352.57  4880.0 1350.50
  4982.9 1347.78  4991.3 1345.35  5009.5 1343.94  5009.9 1343.44  5014.7 1343.94
  5019.2 1345.68  5054.6 1347.61  5167.7 1347.75  5224.3 1349.04  5280.8 1351.96
  5344.5 1352.37  5478.8 1356.99  5648.5 1358.77  5761.7 1361.60  5797.0 1363.74
  5818.3 1363.34  6157.7 1376.46  6228.4 1380.09  6235.4 1381.44  6313.2 1384.39
#Mann=3,-1,0
  3828.2    0.05       0  5009.5   0.035       0  5014.7    0.05       0
Bank Sta=5009.5,5014.7
Exp/Cntr=0.3,0.1

Type RM Length L Ch R = 1,45500,500,500,500
BEGIN DESCRIPTION:
BENNETT CREEK 91.0
END DESCRIPTION:
XS GIS Cut Line= 3
      2778355.71     10192803.11      2779347.61     10192906.75
      2779605.71     10193003.12
#Sta/Elev= 30
  4002.7 1364.65  4083.1 1361.75  4103.2 1360.41  4123.3 1357.85  4147.7 1356.38
  4153.5 1355.52  4294.3 1348.64  4314.4 1348.35  4364.6 1346.17  4425.0 1346.44
  4465.2 1345.79  4565.7 1347.21  4676.3 1346.91  4728.0 1348.02  4736.6 1347.48
  4797.0 1347.57  4816.3 1349.34  4837.2 1346.94  4897.5 1343.48  4914.7 1341.73
  4993.9 1341.51  4994.3 1341.01  4998.8 1341.01  4999.2 1341.51  5033.9 1341.66
  5058.9 1348.98  5089.2 1353.86  5222.1 1361.80  5254.1 1362.19  5275.5 1361.60
#Mann=3,-1,0
  4002.7    0.05       0  4993.9    0.05       0  4999.2    0.05       0
Bank Sta=4993.9,4999.2
Exp/Cntr=0.3,0.1

Type RM Length L Ch R = 1,45000,500,500,500
BEGIN DESCRIPTION:
BENNETT CREEK 90.0
END DESCRIPTION:
XS GIS Cut Line= 3
      2778305.72     10192903.12      2778985.32     10193169.37
      2779955.72     10194103.15
#Sta/Elev= 30
  4270.1 1366.29  4463.4 1352.01  4592.3 1345.96  4719.1 1343.10  4941.5 1342.65
  4946.9 1341.50  4966.0 1341.46  4993.1 1339.78  4993.5 1339.28  4998.4 1339.78
  5031.1 1342.60  5158.5 1346.64  5427.3 1352.78  5604.0 1355.36  5660.6 1357.79
  5681.7 1357.07  5780.8 1359.69  5802.1 1361.42  5865.7 1362.37  5929.5 1365.59
  5964.7 1365.61  6007.2 1368.60  6028.3 1367.91  6035.5 1369.17  6141.5 1372.64
  6198.1 1376.73  6205.3 1378.15  6240.5 1378.68  6286.9 1384.42  6346.7 1392.99
#Mann=4,-1,0
  4270.1    0.05       0  4993.1    0.03       0  4998.4    0.05       0
  6286.9    0.12       0
Bank Sta=4993.1,4998.4
Exp/Cntr=0.3,0.1

Type RM Length L Ch R = 1,44500,500,500,500
BEGIN DESCRIPTION:
BENNETT CREEK 89.0
END DESCRIPTION:
XS GIS Cut Line= 3
      2778255.72     10193003.14      2778593.99     10193348.88
      2779555.71     10194303.13
#Sta/Elev= 30
  4516.3 1363.16  4636.5 1357.21  4685.9 1352.09  4799.1 1345.37  4855.6 1343.05
  4933.5 1342.65  4961.8 1341.31  4990.1 1338.19  4994.3 1335.51  4994.7 1335.01
  4999.8 1335.51  5004.7 1335.65  5011.3 1338.71  5018.3 1338.40  5025.4 1340.05
  5188.0 1340.33  5237.5 1341.69  5485.0 1343.54  5866.9 1351.49  6008.3 1355.24
  6050.7 1357.39  6079.0 1357.41  6114.4 1358.87  6135.6 1360.85  6163.8 1360.82
  6262.8 1364.99  6269.9 1366.22  6312.4 1367.61  6319.4 1366.91  6354.8 1368.80
#Mann=3,-1,0
  4516.3    0.05       0  4994.3    0.03       0  4999.8    0.05       0
Bank Sta=4994.3,4999.8
Exp/Cntr=0.3,0.1

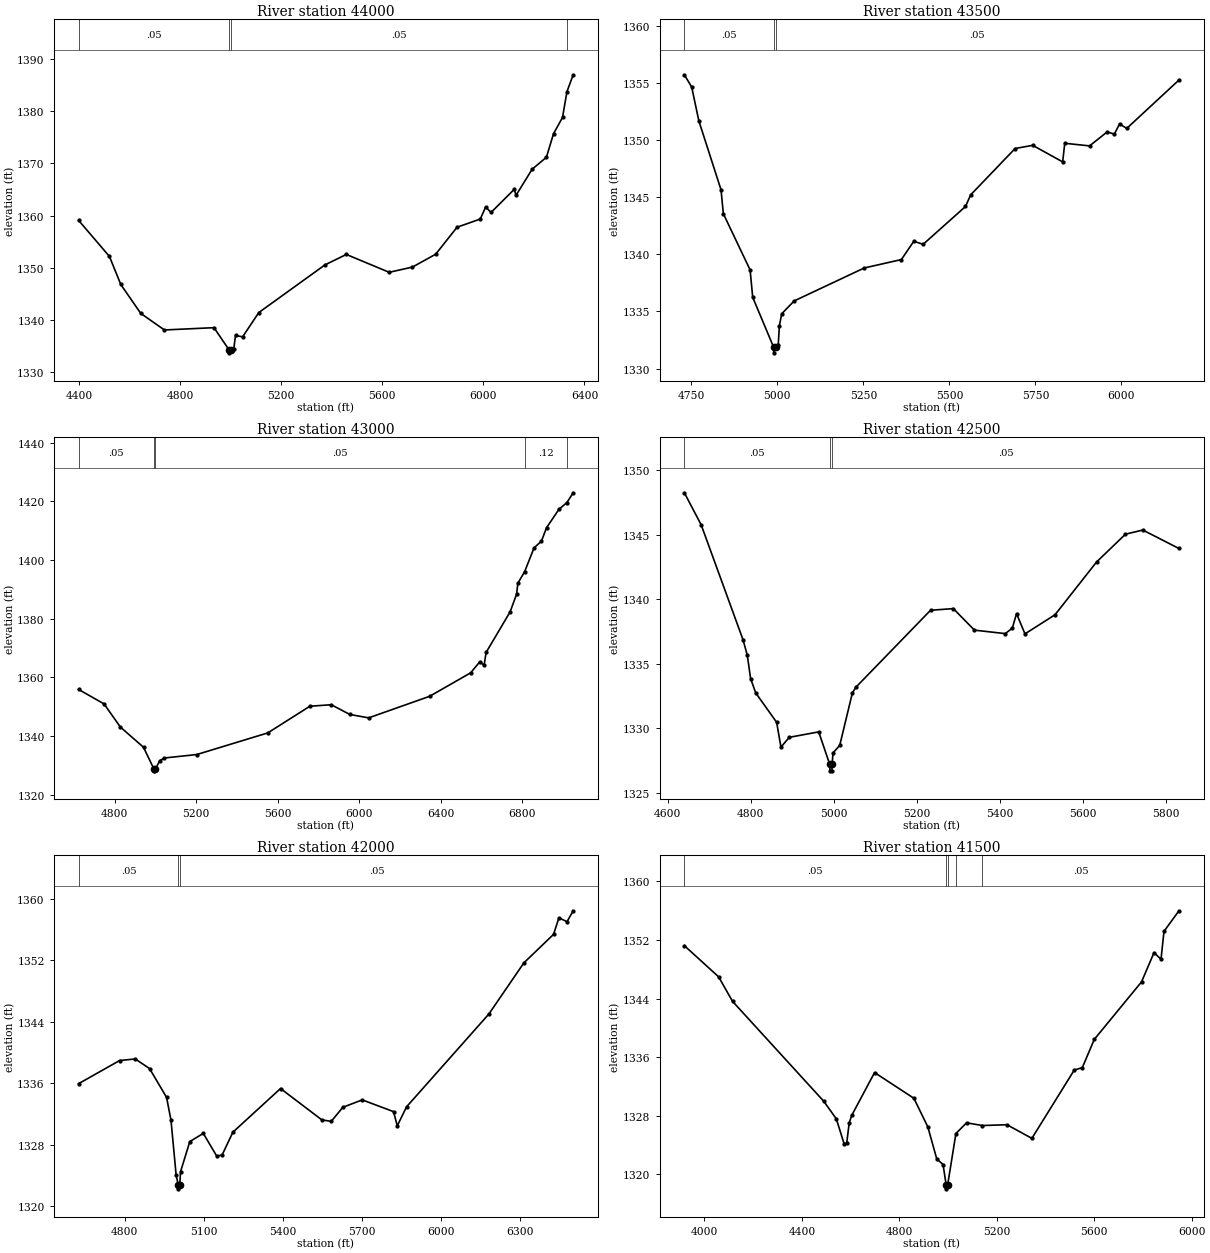
Type RM Length L Ch R = 1,44000,500,500,500
BEGIN DESCRIPTION:
BENNETT CREEK 88.0
END DESCRIPTION:
XS GIS Cut Line= 3
      2778055.70     10193453.12      2778560.74     10193781.49
      2779505.65     10194753.08
#Sta/Elev= 30
  4397.6 1359.11  4519.8 1352.19  4564.6 1346.83  4643.7 1341.29  4737.2 1338.12
  4933.6 1338.56  4994.0 1334.24  4994.5 1333.74  4999.7 1334.24  5011.7 1334.45
  5018.7 1337.06  5047.0 1336.81  5110.8 1341.45  5372.4 1350.57  5457.3 1352.58
  5627.0 1349.16  5718.9 1350.16  5810.9 1352.62  5895.6 1357.79  5987.6 1359.36
  6008.8 1361.67  6030.1 1360.62  6121.9 1365.04  6129.1 1363.91  6192.7 1368.89
  6249.3 1371.19  6277.5 1375.70  6313.0 1378.81  6330.6 1383.76  6355.3 1386.98
#Mann=4,-1,0
  4397.6    0.05       0  4994.0    0.05       0  4999.7    0.05       0
  6330.6    0.12       0
Bank Sta=4994,4999.7
Exp/Cntr=0.3,0.1

Type RM Length L Ch R = 1,43500,500,500,500
BEGIN DESCRIPTION:
BENNETT CREEK 87.0
END DESCRIPTION:
XS GIS Cut Line= 3
      2777955.68     10193703.10      2778134.92     10193905.16
      2779105.65     10194553.09
#Sta/Elev= 30
  4729.9 1355.70  4751.2 1354.63  4772.1 1351.66  4836.5 1345.64  4843.2 1343.55
  4921.0 1338.63  4928.5 1336.24  4989.2 1331.88  4989.7 1331.38  4994.9 1331.88
  5002.7 1332.08  5006.1 1333.77  5012.9 1334.80  5049.0 1335.92  5252.4 1338.80
  5360.6 1339.54  5396.6 1341.14  5423.7 1340.87  5546.8 1344.18  5561.9 1345.20
  5691.0 1349.25  5742.1 1349.53  5829.2 1348.08  5835.2 1349.71  5907.3 1349.48
  5958.4 1350.70  5979.4 1350.51  5994.4 1351.40  6015.4 1351.01  6167.1 1355.24
#Mann=3,-1,0
  4729.9    0.05       0  4989.2    0.05       0  4994.9    0.05       0
Bank Sta=4989.2,4994.9
Exp/Cntr=0.3,0.1

Type RM Length L Ch R = 1,43000,500,500,500
BEGIN DESCRIPTION:
BENNETT CREEK 86.0
END DESCRIPTION:
XS GIS Cut Line= 3
      2777605.70     10193903.14      2777785.84     10194234.10
      2779705.71     10194953.12
#Sta/Elev= 30
  4623.2 1355.88  4748.4 1350.94  4828.1 1343.07  4941.8 1336.16  4993.7 1328.63
  4994.2 1328.13  4999.4 1328.63  5021.2 1331.58  5043.9 1332.51  5202.7 1333.68
  5551.5 1341.06  5758.1 1350.16  5863.1 1350.67  5953.9 1347.36  6046.3 1346.19
  6345.3 1353.53  6547.0 1361.55  6590.9 1365.24  6612.9 1364.17  6622.9 1368.52
  6740.4 1382.32  6772.4 1388.36  6778.5 1392.10  6811.8 1396.03  6857.9 1404.15
  6894.2 1406.44  6919.2 1411.01  6979.7 1417.26  7019.3 1419.62  7050.1 1422.94
#Mann=5,-1,0
  4623.2    0.05       0  4993.7    0.05       0  4999.4    0.05       0
  6811.8    0.12       0  7019.3    0.05       0
Bank Sta=4993.7,4999.4
Exp/Cntr=0.3,0.1

Type RM Length L Ch R = 1,42500,500,500,500
BEGIN DESCRIPTION:
BENNETT CREEK 85.0
END DESCRIPTION:
XS GIS Cut Line= 3
      2777305.65     10194603.11      2777661.26     10194658.51
      2778481.57     10194799.29
#Sta/Elev= 30
  4640.1 1348.24  4680.6 1345.76  4781.8 1336.82  4791.9 1335.63  4799.8 1333.83
  4812.2 1332.72  4862.6 1330.44  4872.9 1328.52  4893.1 1329.28  4964.0 1329.70
  4990.5 1327.18  4991.0 1326.68  4995.8 1326.68  4996.3 1327.18  4998.4 1328.07
  5014.6 1328.65  5045.1 1332.72  5053.5 1333.16  5233.5 1339.13  5288.4 1339.26
  5339.3 1337.59  5413.5 1337.32  5430.6 1337.74  5440.8 1338.87  5461.1 1337.30
  5533.5 1338.78  5633.6 1342.87  5703.3 1345.03  5745.2 1345.35  5832.3 1343.92
#Mann=3,-1,0
  4640.1    0.05       0  4990.5    0.05       0  4996.3    0.05       0
Bank Sta=4990.5,4996.3
Exp/Cntr=0.3,0.1

Type RM Length L Ch R = 1,42000,500,500,500
BEGIN DESCRIPTION:
BENNETT CREEK 84.0
END DESCRIPTION:
XS GIS Cut Line= 3
      2777050.09     10194960.88      2777419.00     10195025.36
      2778888.67     10195341.10
#Sta/Elev= 30
  4625.5 1335.94  4781.0 1338.95  4840.5 1339.16  4894.9 1337.91  4959.5 1334.16
  4976.3 1331.18  4995.8 1324.05  5003.9 1322.75  5004.4 1322.25  5009.7 1322.75
  5012.5 1324.47  5047.7 1328.40  5098.9 1329.47  5150.0 1326.51  5170.5 1326.67
  5211.4 1329.63  5392.2 1335.31  5548.9 1331.23  5584.6 1331.03  5628.8 1332.87
  5702.4 1333.83  5821.2 1332.30  5835.3 1330.45  5870.6 1332.93  6183.1 1345.01
  6316.0 1351.67  6428.6 1355.38  6449.0 1357.53  6479.7 1357.03  6503.2 1358.45
#Mann=3,-1,0
  4625.5    0.05       0  5003.9    0.05       0  5009.7    0.05       0
Bank Sta=5003.9,5009.7
Exp/Cntr=0.3,0.1

Type RM Length L Ch R = 1,41500,500,500,500
BEGIN DESCRIPTION:
BENNETT CREEK 83.0
END DESCRIPTION:
XS GIS Cut Line= 3
      2776605.66     10195803.12      2777629.37     10195451.25
      2778555.73     10195653.12
#Sta/Elev= 30
  3917.5 1351.22  4058.1 1346.97  4115.3 1343.62  4490.2 1329.97  4541.4 1327.58
  4573.1 1324.21  4584.0 1324.25  4594.3 1327.05  4604.6 1328.05  4698.4 1333.90
  4859.9 1330.39  4917.1 1326.48  4953.8 1322.11  4979.6 1321.35  4992.5 1318.53
  4993.0 1318.03  4998.3 1318.53  5032.4 1325.58  5076.1 1327.04  5141.1 1326.67
  5241.9 1326.78  5344.2 1324.92  5518.2 1334.24  5551.4 1334.58  5600.5 1338.43
  5794.5 1346.28  5845.7 1350.27  5874.4 1349.36  5886.6 1353.17  5948.1 1355.98
#Mann=5,-1,0
  3917.5    0.05       0  4992.5    0.03       0  4998.3    0.05       0
  5032.4    0.12       0  5141.1    0.05       0
Bank Sta=4992.5,4998.3
Exp/Cntr=0.3,0.1

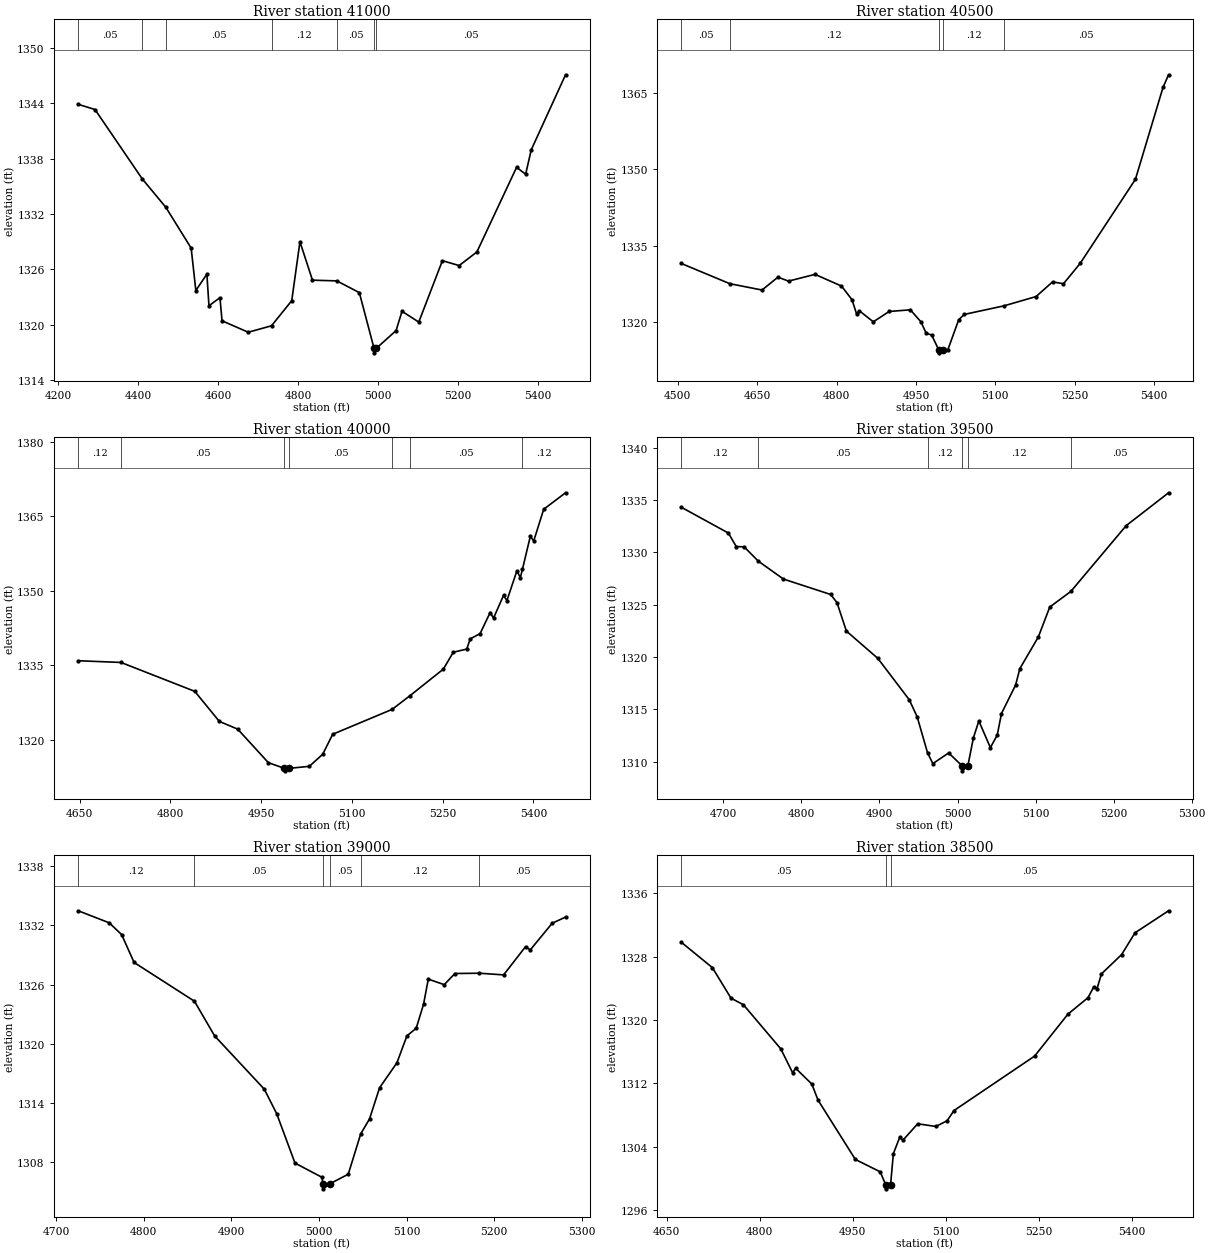
Type RM Length L Ch R = 1,41000,500,500,500
BEGIN DESCRIPTION:
BENNETT CREEK 82.0
END DESCRIPTION:
XS GIS Cut Line= 3
      2777105.64     10196103.12      2777822.82     10195883.34
      2778205.72     10196153.14
#Sta/Elev= 30
  4249.9 1343.87  4291.8 1343.31  4410.1 1335.79  4468.8 1332.73  4532.3 1328.30
  4544.0 1323.71  4571.6 1325.48  4576.8 1322.06  4604.3 1322.93  4609.5 1320.43
  4675.0 1319.19  4733.2 1319.89  4783.8 1322.61  4804.3 1328.99  4835.6 1324.83
  4896.6 1324.75  4952.8 1323.48  4989.5 1317.46  4990.0 1316.96  4995.5 1317.46
  5044.7 1319.37  5059.5 1321.46  5101.4 1320.29  5160.5 1326.94  5202.3 1326.41
  5246.7 1327.88  5346.0 1337.05  5368.6 1336.30  5382.7 1338.95  5468.4 1347.07
#Mann=7,-1,0
  4249.9    0.05       0  4410.1    0.12       0  4468.8    0.05       0
  4733.2    0.12       0  4896.6    0.05       0  4989.5    0.05       0
  4995.5    0.05       0
Bank Sta=4989.5,4995.5
Exp/Cntr=0.3,0.1

Type RM Length L Ch R = 1,40500,500,500,500
BEGIN DESCRIPTION:
BENNETT CREEK 81.0
END DESCRIPTION:
XS GIS Cut Line= 3
      2777253.21     10196351.51      2777746.11     10196331.77
      2778155.72     10196453.12
#Sta/Elev= 30
  4506.7 1331.53  4598.5 1327.56  4659.3 1326.32  4689.3 1328.84  4709.3 1328.07
  4759.4 1329.39  4809.4 1327.10  4829.4 1324.40  4838.0 1321.59  4843.0 1322.26
  4869.5 1320.09  4899.5 1322.12  4939.5 1322.44  4959.5 1320.08  4969.5 1317.82
  4979.6 1317.52  4993.5 1314.51  4994.0 1314.01  5001.1 1314.51  5010.0 1314.53
  5030.8 1320.49  5041.3 1321.54  5116.7 1323.23  5176.9 1325.04  5208.1 1327.92
  5228.7 1327.55  5260.3 1331.55  5364.6 1348.02  5416.7 1366.03  5427.2 1368.51
#Mann=5,-1,0
  4506.7    0.05       0  4598.5    0.12       0  4993.5    0.07       0
  5001.1    0.12       0  5116.7    0.05       0
Bank Sta=4993.5,5001.1
Exp/Cntr=0.3,0.1

Type RM Length L Ch R = 1,40000,500,500,500
BEGIN DESCRIPTION:
BENNETT CREEK 80.0
END DESCRIPTION:
XS GIS Cut Line= 3
      2777355.70     10196753.11      2777703.29     10196811.11
      2778105.71     10196603.10
#Sta/Elev= 30
  4647.6 1335.96  4718.4 1335.61  4840.2 1329.80  4880.8 1323.75  4911.2 1322.19
  4961.9 1315.44  4988.5 1314.30  4989.0 1313.80  4996.1 1314.30  5029.6 1314.71
  5051.7 1317.14  5068.2 1321.16  5166.4 1326.17  5196.3 1328.96  5251.0 1334.27
  5267.5 1337.67  5289.7 1338.30  5295.4 1340.35  5311.8 1341.42  5328.4 1345.66
  5334.0 1344.54  5350.5 1349.10  5356.1 1348.07  5372.6 1354.05  5378.3 1352.68
  5381.8 1354.38  5394.8 1361.00  5400.4 1360.06  5416.9 1366.44  5453.0 1369.76
#Mann=7,-1,0
  4647.6    0.12       0  4718.4    0.05       0  4988.5    0.05       0
  4996.1    0.05       0  5166.4    0.12       0  5196.3    0.05       0
  5381.8    0.12       0
Bank Sta=4988.5,4996.1
Exp/Cntr=0.3,0.1

Type RM Length L Ch R = 1,39500,500,500,500
BEGIN DESCRIPTION:
BENNETT CREEK 79.0
END DESCRIPTION:
XS GIS Cut Line= 3
      2777305.72     10197253.12      2777657.01     10197296.80
      2777905.64     10197403.09
#Sta/Elev= 30
  4646.0 1334.31  4706.4 1331.84  4716.5 1330.55  4726.6 1330.52  4744.8 1329.15
  4777.0 1327.44  4837.4 1325.97  4845.5 1325.20  4857.6 1322.47  4897.9 1319.86
  4938.2 1315.90  4948.3 1314.27  4961.6 1310.83  4968.4 1309.80  4988.6 1310.82
  5005.6 1309.61  5006.1 1309.11  5013.3 1309.61  5020.3 1312.25  5027.3 1313.88
  5042.1 1311.33  5050.9 1312.53  5056.3 1314.59  5074.4 1317.31  5079.9 1318.89
  5103.5 1321.90  5118.2 1324.77  5145.2 1326.26  5216.1 1332.55  5270.4 1335.69
#Mann=6,-1,0
  4646.0    0.12       0  4744.8    0.05       0  4961.6    0.12       0
  5005.6    0.07       0  5013.3    0.12       0  5145.2    0.05       0
Bank Sta=5005.6,5013.3
Exp/Cntr=0.3,0.1

Type RM Length L Ch R = 1,39000,500,500,500
BEGIN DESCRIPTION:
BENNETT CREEK 78.0
END DESCRIPTION:
XS GIS Cut Line= 3
      2777205.71     10197503.14      2777391.50     10197705.76
      2777655.64     10197803.09
#Sta/Elev= 30
  4725.1 1333.48  4760.5 1332.26  4774.7 1331.06  4788.9 1328.24  4857.8 1324.31
  4880.8 1320.80  4937.5 1315.40  4951.7 1312.91  4972.6 1307.90  5003.4 1306.46
  5004.4 1305.79  5004.9 1305.29  5012.1 1305.79  5033.4 1306.77  5047.6 1310.85
  5057.7 1312.38  5069.2 1315.54  5089.0 1318.07  5100.4 1320.80  5111.0 1321.57
  5119.4 1324.01  5124.8 1326.55  5143.0 1325.99  5155.2 1327.12  5183.2 1327.15
  5210.8 1326.98  5235.9 1329.85  5241.2 1329.51  5266.3 1332.22  5281.5 1332.84
#Mann=6,-1,0
  4725.1    0.12       0  4857.8    0.05       0  5004.4    0.05       0
  5012.1    0.05       0  5047.6    0.12       0  5183.2    0.05       0
Bank Sta=5004.4,5012.1
Exp/Cntr=0.3,0.1

Type RM Length L Ch R = 1,38500,500,500,500
BEGIN DESCRIPTION:
BENNETT CREEK 77.0
END DESCRIPTION:
XS GIS Cut Line= 3
      2776955.64     10198153.11      2777281.15     10198179.78
      2777705.66     10198003.12
#Sta/Elev= 30
  4673.4 1329.82  4723.6 1326.61  4753.7 1322.75  4773.8 1321.91  4834.0 1316.35
  4853.1 1313.33  4858.1 1313.89  4884.1 1311.90  4894.2 1309.86  4954.4 1302.37
  4994.5 1300.81  5003.4 1299.16  5003.9 1298.66  5011.2 1299.16  5015.7 1303.10
  5025.8 1305.15  5031.2 1304.81  5055.0 1306.88  5084.3 1306.54  5102.4 1307.26
  5113.5 1308.55  5243.6 1315.43  5297.4 1320.73  5329.8 1322.81  5339.0 1324.16
  5344.4 1323.97  5351.5 1325.82  5384.0 1328.25  5405.7 1331.01  5459.8 1333.79
#Mann=3,-1,0
  4673.4    0.05       0  5003.4    0.05       0  5011.2    0.05       0
Bank Sta=5003.4,5011.2
Exp/Cntr=0.3,0.1

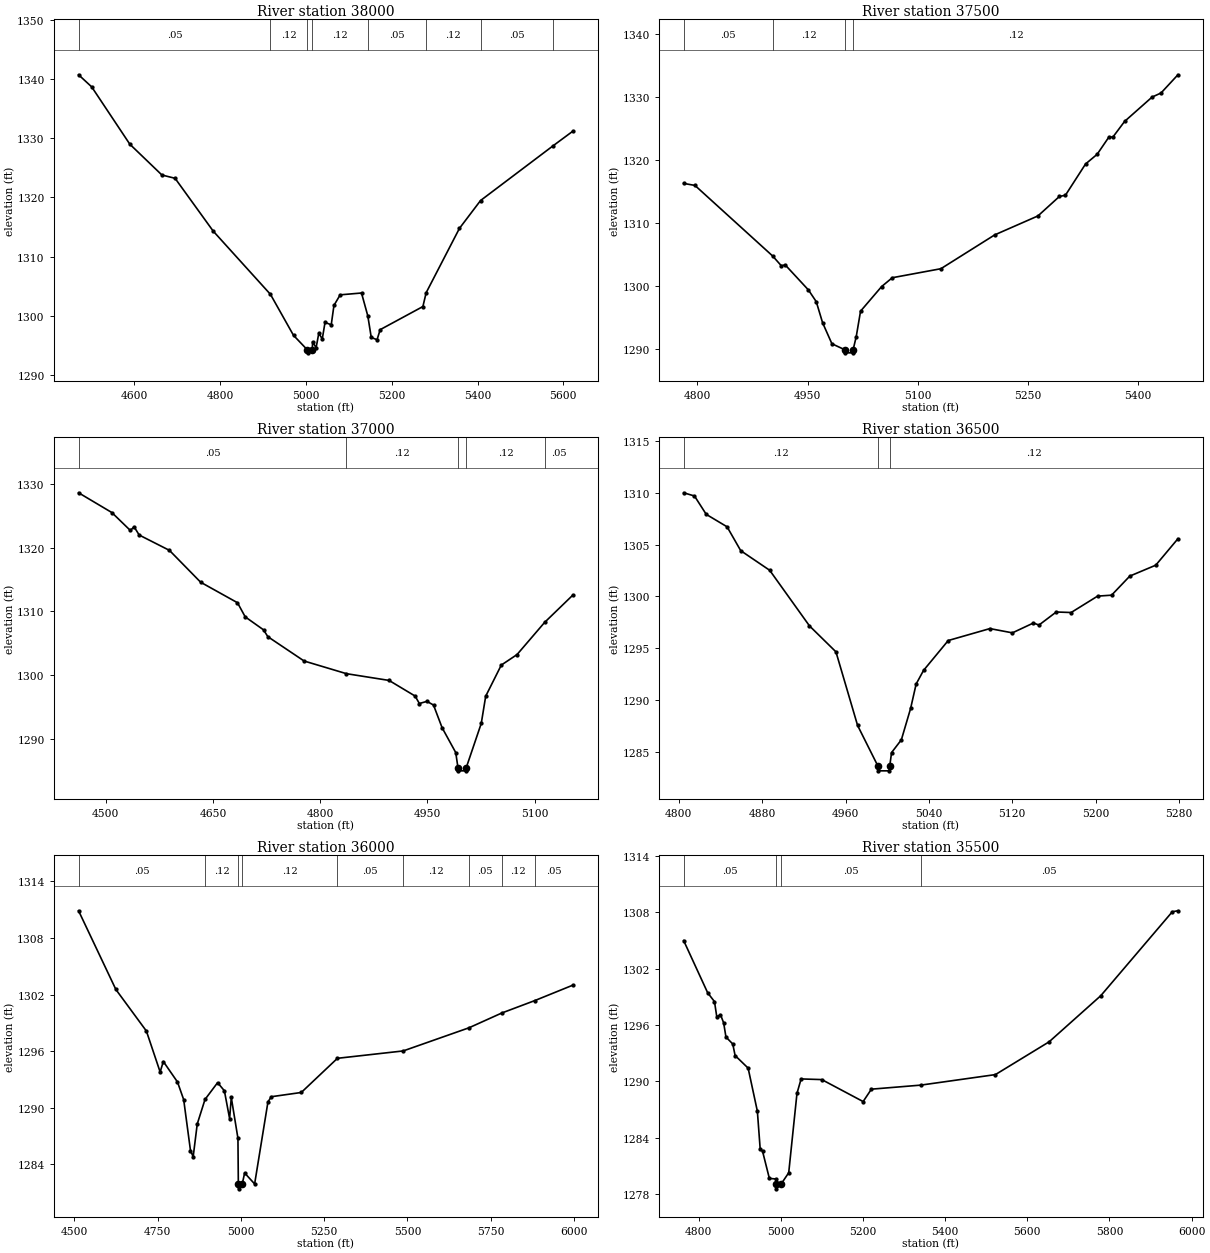
Type RM Length L Ch R = 1,38000,500,500,500
BEGIN DESCRIPTION:
BENNETT CREEK 76.0
END DESCRIPTION:
XS GIS Cut Line= 3
      2776905.73     10198753.10      2777423.68     10198644.09
      2777805.69     10198153.10
#Sta/Elev= 30
  4470.7 1340.74  4501.3 1338.69  4590.1 1329.00  4664.8 1323.79  4695.5 1323.23
  4784.3 1314.30  4917.7 1303.60  4971.4 1296.67  5003.7 1294.21  5004.2 1293.71
  5015.2 1294.21  5015.8 1295.59  5024.0 1294.56  5030.3 1297.02  5038.4 1296.06
  5044.8 1298.85  5059.3 1298.46  5065.6 1301.73  5080.1 1303.52  5129.8 1303.83
  5144.5 1299.95  5152.5 1296.31  5166.0 1295.93  5173.3 1297.63  5272.8 1301.54
  5280.4 1303.88  5357.9 1314.76  5407.1 1319.47  5574.8 1328.66  5622.1 1331.20
#Mann=8,-1,0
  4470.7    0.05       0  4917.7    0.12       0  5003.7    0.07       0
  5015.2    0.12       0  5144.5    0.05       0  5280.4    0.12       0
  5407.1    0.05       0  5574.8    0.12       0
Bank Sta=5003.7,5015.2
Exp/Cntr=0.3,0.1

Type RM Length L Ch R = 1,37500,500,500,500
BEGIN DESCRIPTION:
BENNETT CREEK 75.0
END DESCRIPTION:
XS GIS Cut Line= 3
      2777155.68     10199053.11      2777361.52     10199127.01
      2777755.67     10199353.11
#Sta/Elev= 30
  4781.3 1316.36  4796.7 1316.04  4902.5 1304.84  4914.3 1303.29  4919.6 1303.43
  4951.3 1299.44  4961.9 1297.59  4970.5 1294.25  4983.2 1290.91  5000.6 1289.97
  5001.1 1289.47  5011.6 1289.47  5012.1 1289.97  5016.3 1292.02  5022.2 1296.08
  5050.9 1299.99  5065.4 1301.39  5131.6 1302.82  5204.9 1308.19  5263.8 1311.20
  5293.0 1314.29  5301.2 1314.48  5328.6 1319.44  5344.4 1320.98  5360.2 1323.68
  5366.0 1323.74  5381.8 1326.20  5419.2 1330.06  5431.4 1330.71  5454.4 1333.60
#Mann=4,-1,0
  4781.3    0.05       0  4902.5    0.12       0  5000.6    0.07       0
  5012.1    0.12       0
Bank Sta=5000.6,5012.1
Exp/Cntr=0.3,0.1

Type RM Length L Ch R = 1,37000,500,500,500
BEGIN DESCRIPTION:
BENNETT CREEK 74.0
END DESCRIPTION:
XS GIS Cut Line= 3
      2776655.65     10199403.10      2777163.57     10199580.49
      2777255.71     10199703.14
#Sta/Elev= 30
  4462.0 1328.65  4508.6 1325.54  4534.4 1322.73  4539.7 1323.30  4546.8 1322.01
  4589.1 1319.60  4632.8 1314.59  4684.3 1311.37  4695.1 1309.15  4720.7 1307.11
  4726.8 1306.03  4777.5 1302.21  4836.7 1300.22  4896.3 1299.16  4932.8 1296.70
  4938.7 1295.53  4949.3 1295.87  4958.5 1295.29  4970.5 1291.73  4989.6 1287.82
  4992.7 1285.45  4993.2 1284.95  5003.8 1284.95  5004.3 1285.45  5025.3 1292.41
  5031.5 1296.68  5053.3 1301.57  5075.3 1303.22  5114.0 1308.29  5153.4 1312.57
#Mann=5,-1,0
  4462.0    0.05       0  4836.7    0.12       0  4992.7    0.07       0
  5004.3    0.12       0  5114.0    0.05       0
Bank Sta=4992.7,5004.3
Exp/Cntr=0.3,0.1

Type RM Length L Ch R = 1,36500,500,500,500
BEGIN DESCRIPTION:
BENNETT CREEK 73.0
END DESCRIPTION:
XS GIS Cut Line= 3
      2776605.71     10199853.12      2776792.85     10199909.34
      2777055.72     10200003.12
#Sta/Elev= 30
  4804.6 1309.99  4815.0 1309.68  4826.3 1307.91  4846.3 1306.71  4859.4 1304.41
  4887.2 1302.52  4925.4 1297.16  4950.8 1294.66  4971.6 1287.56  4990.9 1283.69
  4991.4 1283.19  5002.0 1283.19  5002.5 1283.69  5004.2 1284.95  5013.6 1286.18
  5022.5 1289.21  5027.8 1291.56  5034.9 1292.87  5058.6 1295.75  5098.6 1296.90
  5120.2 1296.49  5140.4 1297.44  5145.7 1297.24  5162.3 1298.50  5176.6 1298.45
  5202.0 1300.03  5215.4 1300.12  5232.9 1301.96  5257.8 1303.01  5279.1 1305.56
#Mann=3,-1,0
  4804.6    0.12       0  4990.9    0.07       0  5002.5    0.12       0
Bank Sta=4990.9,5002.5
Exp/Cntr=0.3,0.1

Type RM Length L Ch R = 1,36000,500,500,500
BEGIN DESCRIPTION:
BENNETT CREEK 72.0
END DESCRIPTION:
XS GIS Cut Line= 3
      2776105.66     10200453.12      2776584.44     10200361.83
      2777580.98     10200372.34
#Sta/Elev= 30
  4512.6 1310.88  4624.6 1302.54  4716.2 1298.14  4757.5 1293.80  4767.1 1294.91
  4809.6 1292.74  4828.2 1290.87  4848.6 1285.48  4856.7 1284.82  4868.9 1288.29
  4892.2 1290.89  4930.0 1292.67  4950.4 1291.81  4966.1 1288.86  4971.1 1291.10
  4991.1 1286.77  4992.3 1281.92  4992.8 1281.42  5003.9 1281.92  5011.2 1283.10
  5041.2 1281.94  5081.2 1290.63  5091.3 1291.18  5181.3 1291.63  5289.8 1295.25
  5487.2 1296.03  5684.6 1298.48  5783.3 1300.05  5882.0 1301.36  5996.6 1303.00
#Mann=9,-1,0
  4512.6    0.05       0  4892.2    0.12       0  4992.3    0.07       0
  5003.9    0.12       0  5289.8    0.05       0  5487.2    0.12       0
  5684.6    0.05       0  5783.3    0.12       0  5882.0    0.05       0
Bank Sta=4992.3,5003.9
Exp/Cntr=0.3,0.1

Type RM Length L Ch R = 1,35500,500,500,500
BEGIN DESCRIPTION:
BENNETT CREEK 71.0
END DESCRIPTION:
XS GIS Cut Line= 3
      2776305.66     10200953.12      2776516.80     10200845.91
      2777477.24     10200736.92
#Sta/Elev= 30
  4763.2 1304.98  4821.7 1299.42  4838.3 1298.48  4843.9 1296.86  4852.9 1297.09
  4860.6 1296.22  4866.2 1294.71  4882.8 1293.97  4888.5 1292.74  4920.2 1291.40
  4942.7 1286.81  4949.6 1282.76  4955.2 1282.57  4971.9 1279.66  4987.5 1279.60
  4987.9 1279.05  4988.4 1278.55  5000.3 1279.05  5019.0 1280.26  5039.1 1288.71
  5049.2 1290.25  5099.5 1290.18  5200.2 1287.84  5220.3 1289.16  5340.4 1289.59
  5522.2 1290.71  5653.0 1294.20  5778.8 1299.11  5953.0 1308.05  5966.6 1308.15
#Mann=4,-1,0
  4763.2    0.05       0  4987.9    0.07       0  5000.3    0.05       0
  5340.4    0.05       0
Bank Sta=4987.9,5000.3
Exp/Cntr=0.3,0.1