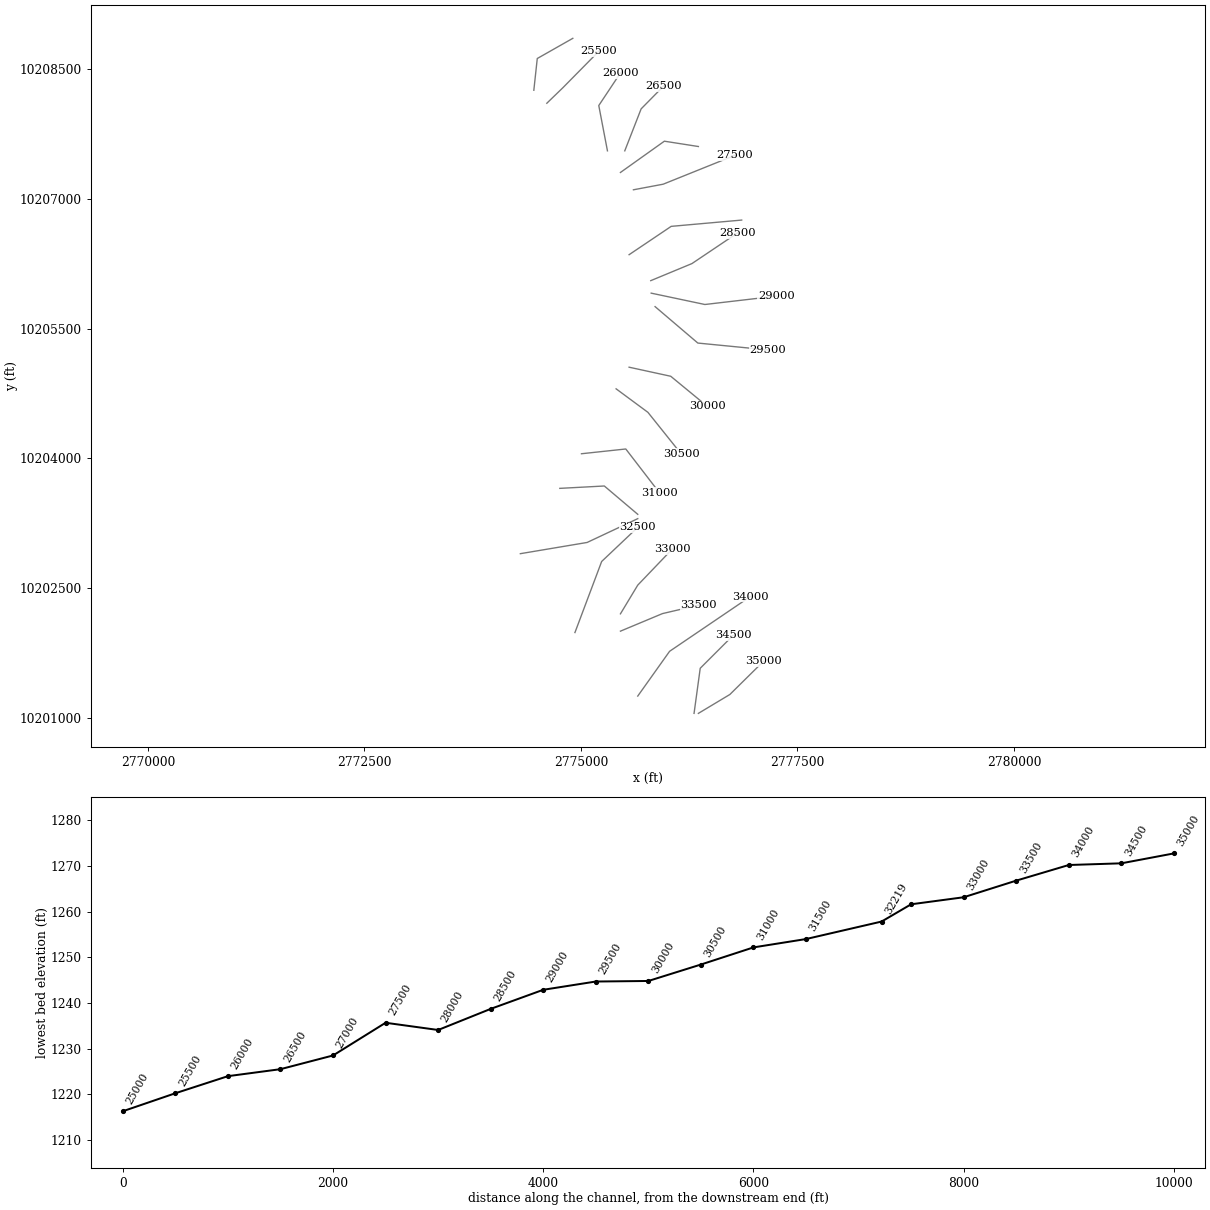
HEC-RAS study BENNETT CREEK.prj: BENNETT CREEK Base Level Engineering

--- BENNETT CREEK.g01 (geometry) --- (continued)

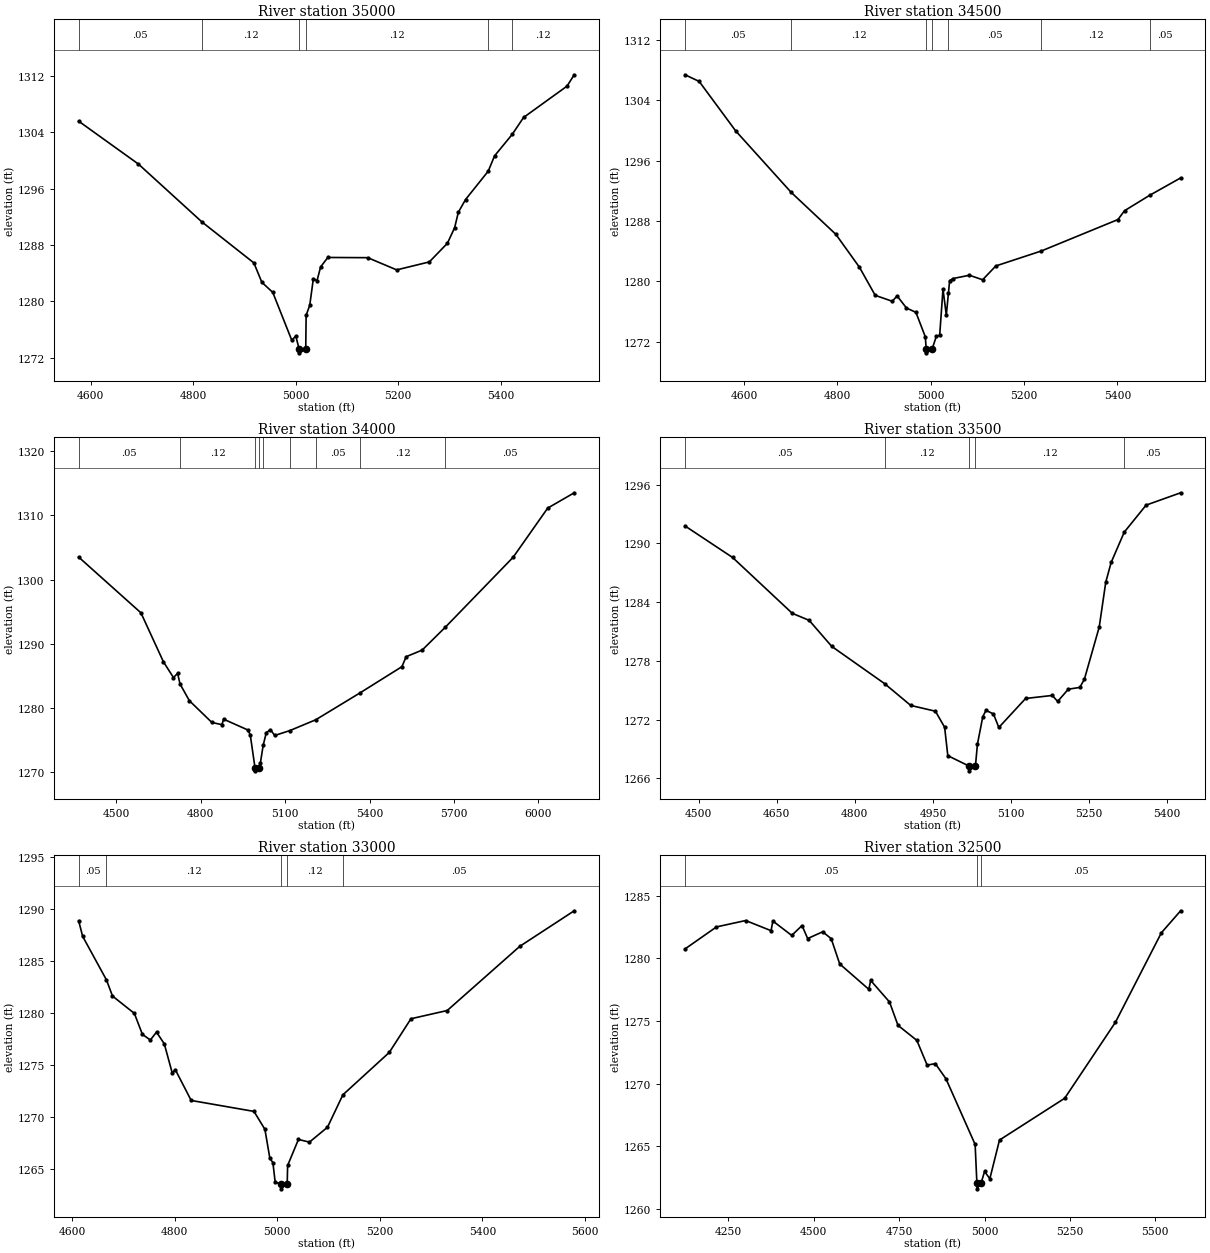
Type RM Length L Ch R = 1,35000,500,500,500
BEGIN DESCRIPTION:
BENNETT CREEK 70.0
END DESCRIPTION:
XS GIS Cut Line= 3
      2776355.67     10201053.11      2776719.00     10201271.28
      2777105.66     10201653.09
#Sta/Elev= 30
  4576.2 1305.54  4692.9 1299.46  4816.7 1291.27  4918.2 1285.46  4933.8 1282.71
  4955.1 1281.28  4992.1 1274.51  5000.0 1275.09  5006.7 1273.22  5007.2 1272.72
  5019.4 1273.22  5020.2 1278.05  5027.2 1279.44  5034.3 1283.23  5041.4 1282.94
  5048.5 1284.90  5062.6 1286.23  5140.4 1286.20  5196.9 1284.47  5260.6 1285.60
  5295.9 1288.24  5310.1 1290.47  5317.2 1292.63  5331.3 1294.44  5375.6 1298.46
  5387.9 1300.62  5422.3 1303.66  5444.5 1306.06  5529.3 1310.50  5543.4 1312.11
#Mann=6,-1,0
  4576.2    0.05       0  4816.7    0.12       0  5006.7    0.07       0
  5019.4    0.12       0  5375.6    0.05       0  5422.3    0.12       0
Bank Sta=5006.7,5019.4
Exp/Cntr=0.3,0.1

Type RM Length L Ch R = 1,34500,500,500,500
BEGIN DESCRIPTION:
BENNETT CREEK 69.0
END DESCRIPTION:
XS GIS Cut Line= 3
      2776305.68     10201053.09      2776376.95     10201574.34
      2776755.66     10201953.08
#Sta/Elev= 30
  4473.9 1307.35  4504.2 1306.47  4582.3 1299.93  4701.4 1291.78  4796.9 1286.24
  4847.4 1281.89  4881.3 1278.16  4918.0 1277.37  4928.1 1278.09  4948.3 1276.48
  4968.5 1275.91  4988.7 1272.66  4990.5 1271.05  4991.0 1270.55  5003.3 1271.05
  5012.4 1272.77  5019.4 1272.87  5026.5 1278.99  5033.6 1275.53  5038.2 1278.48
  5040.7 1280.09  5047.7 1280.38  5083.1 1280.82  5111.4 1280.22  5139.7 1282.05
  5237.2 1284.03  5401.3 1288.19  5415.4 1289.36  5469.0 1291.39  5535.6 1293.70
#Mann=7,-1,0
  4473.9    0.05       0  4701.4    0.12       0  4990.5    0.07       0
  5003.3    0.12       0  5038.2    0.05       0  5237.2    0.12       0
  5469.0    0.05       0
Bank Sta=4990.5,5003.3
Exp/Cntr=0.3,0.1

Type RM Length L Ch R = 1,34000,500,500,500
BEGIN DESCRIPTION:
BENNETT CREEK 68.0
END DESCRIPTION:
XS GIS Cut Line= 3
      2775655.68     10201253.11      2776023.13     10201770.13
      2776955.70     10202403.12
#Sta/Elev= 30
  4365.7 1303.50  4587.1 1294.81  4667.0 1287.18  4702.7 1284.72  4717.5 1285.37
  4726.0 1283.72  4759.3 1281.11  4839.2 1277.72  4874.9 1277.38  4881.0 1278.23
  4967.1 1276.55  4975.7 1275.79  4992.4 1270.68  4992.9 1270.18  5005.2 1270.68
  5011.7 1271.41  5021.6 1274.16  5032.7 1276.14  5047.6 1276.59  5062.6 1275.69
  5116.1 1276.45  5208.5 1278.14  5365.1 1282.31  5514.8 1286.42  5529.7 1287.97
  5586.6 1289.00  5668.8 1292.56  5910.0 1303.47  6032.8 1311.13  6127.1 1313.52
#Mann=9,-1,0
  4365.7    0.05       0  4726.0    0.12       0  4992.4    0.07       0
  5005.2    0.12       0  5021.6    0.05       0  5116.1    0.12       0
  5208.5    0.05       0  5365.1    0.12       0  5668.8    0.05       0
Bank Sta=4992.4,5005.2
Exp/Cntr=0.3,0.1

Type RM Length L Ch R = 1,33500,500,500,500
BEGIN DESCRIPTION:
BENNETT CREEK 67.0
END DESCRIPTION:
XS GIS Cut Line= 3
      2775455.70     10202003.12      2775941.18     10202206.09
      2776355.68     10202303.11
#Sta/Elev= 30
  4473.8 1291.77  4565.2 1288.55  4679.7 1282.85  4712.2 1282.13  4755.6 1279.47
  4857.0 1275.67  4907.3 1273.44  4954.7 1272.85  4972.4 1271.21  4978.5 1268.31
  5018.8 1267.26  5019.3 1266.76  5031.6 1267.26  5035.4 1269.48  5045.7 1272.29
  5051.8 1272.94  5066.2 1272.57  5076.5 1271.19  5127.9 1274.15  5179.2 1274.46
  5189.5 1273.85  5210.0 1275.10  5232.0 1275.28  5240.8 1276.11  5269.3 1281.44
  5281.9 1286.03  5292.2 1288.04  5317.4 1291.14  5359.4 1293.90  5425.7 1295.16
#Mann=5,-1,0
  4473.8    0.05       0  4857.0    0.12       0  5018.8    0.07       0
  5031.6    0.12       0  5317.4    0.05       0
Bank Sta=5018.8,5031.6
Exp/Cntr=0.3,0.1

Type RM Length L Ch R = 1,33000,500,500,500
BEGIN DESCRIPTION:
BENNETT CREEK 66.0
END DESCRIPTION:
XS GIS Cut Line= 3
      2775455.69     10202203.12      2775655.42     10202534.71
      2776055.67     10202953.09
#Sta/Elev= 30
  4612.9 1288.85  4620.7 1287.35  4667.2 1283.16  4678.9 1281.62  4721.6 1279.95
  4737.2 1277.94  4752.7 1277.40  4764.7 1278.16  4779.9 1277.03  4795.4 1274.23
  4801.3 1274.56  4832.3 1271.60  4954.7 1270.55  4976.0 1268.83  4985.7 1266.04
  4991.6 1265.64  4996.1 1263.73  5006.6 1263.62  5007.1 1263.12  5019.5 1263.62
  5020.3 1265.36  5041.4 1267.86  5062.8 1267.60  5098.0 1269.03  5128.0 1272.14
  5218.5 1276.21  5260.7 1279.44  5331.4 1280.23  5472.9 1286.39  5579.0 1289.80
#Mann=5,-1,0
  4612.9    0.05       0  4667.2    0.12       0  5006.6    0.07       0
  5019.5    0.12       0  5128.0    0.05       0
Bank Sta=5006.6,5019.5
Exp/Cntr=0.3,0.1

Type RM Length L Ch R = 1,32500,281,281,281
BEGIN DESCRIPTION:
BENNETT CREEK 65.0
END DESCRIPTION:
XS GIS Cut Line= 3
      2774930.32     10201986.94      2775238.80     10202808.11
      2775655.69     10203203.11
#Sta/Elev= 30
  4122.8 1280.76  4214.9 1282.52  4300.3 1283.03  4374.7 1282.22  4380.1 1282.99
  4435.2 1281.84  4465.5 1282.63  4481.9 1281.59  4526.0 1282.13  4550.9 1281.58
  4575.8 1279.56  4661.1 1277.53  4666.5 1278.24  4721.6 1276.52  4746.5 1274.65
  4801.7 1273.45  4831.9 1271.47  4855.8 1271.59  4887.0 1270.38  4972.4 1265.13
  4977.5 1262.08  4978.0 1261.58  4990.4 1262.08  5000.0 1262.97  5015.5 1262.39
  5043.8 1265.48  5234.7 1268.82  5383.2 1274.89  5517.9 1282.05  5574.3 1283.81
#Mann=3,-1,0
  4122.8    0.05       0  4977.5    0.05       0  4990.4    0.05       0
Bank Sta=4977.5,4990.4
Exp/Cntr=0.3,0.1

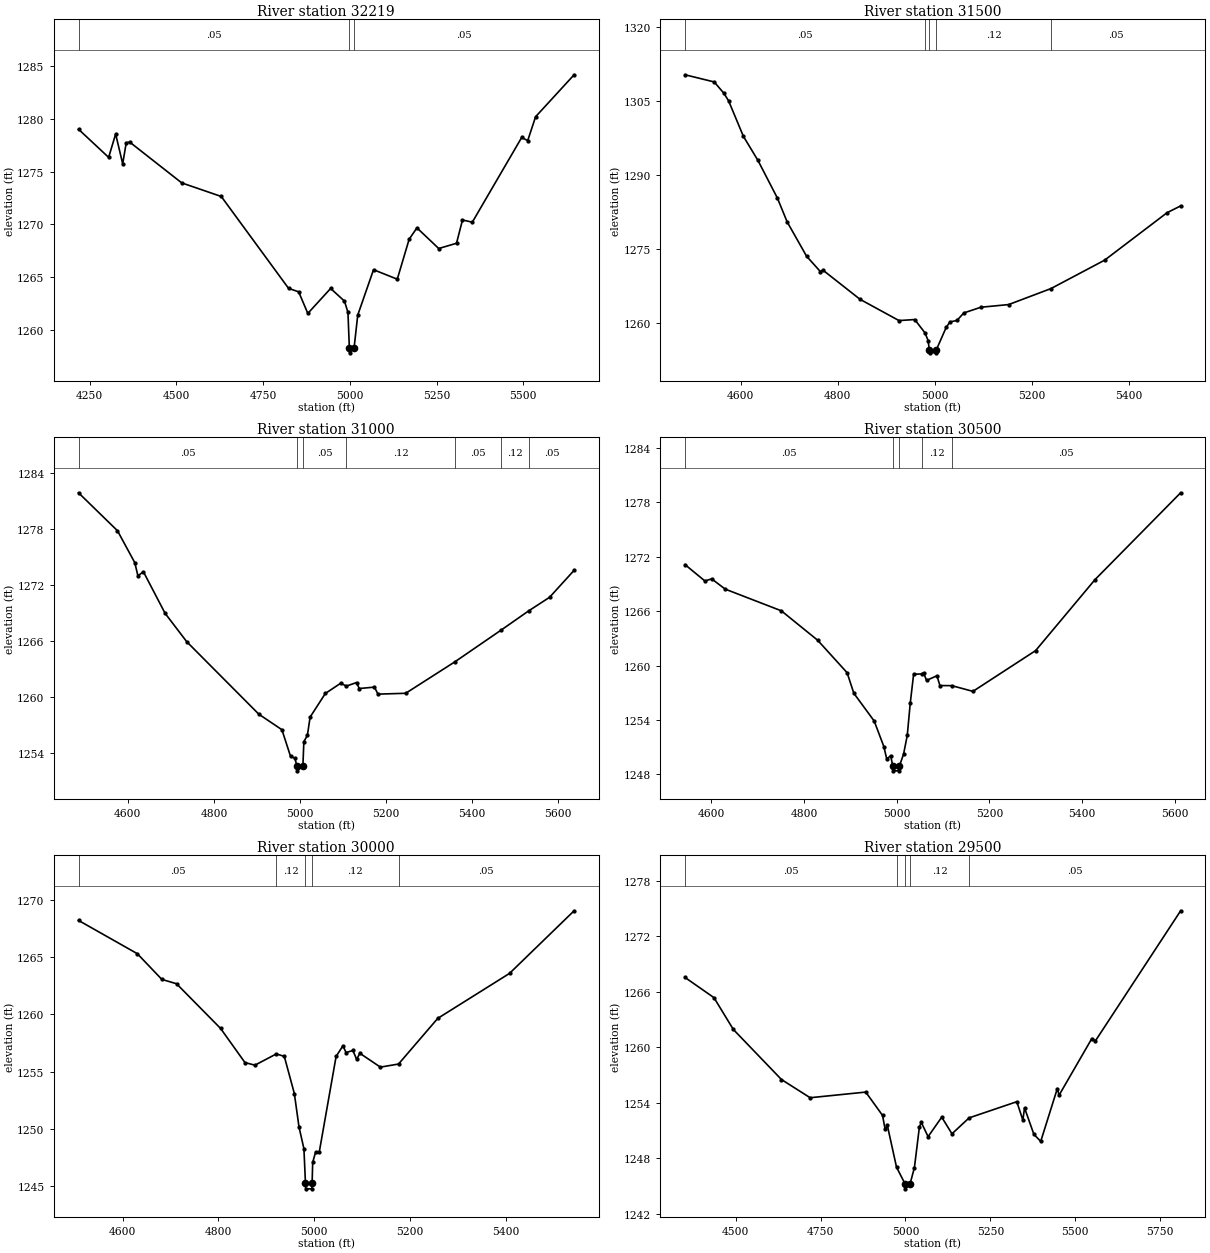
Type RM Length L Ch R = 1,32219,719,719,719
BEGIN DESCRIPTION:
BENNETT CREEK 64.0
END DESCRIPTION:
XS GIS Cut Line= 3
      2774300.12     10202898.39      2775071.00     10203028.00
      2775655.71     10203303.12
#Sta/Elev= 30
  4218.3 1279.02  4305.1 1276.35  4325.3 1278.57  4345.6 1275.74  4355.8 1277.74
  4365.9 1277.80  4515.6 1273.93  4629.6 1272.64  4823.5 1263.92  4852.6 1263.59
  4879.0 1261.54  4944.7 1263.91  4984.5 1262.71  4994.6 1261.65  4998.6 1258.30
  4999.1 1257.80  5012.4 1258.30  5022.8 1261.38  5068.3 1265.69  5136.7 1264.79
  5171.0 1268.59  5193.4 1269.66  5256.2 1267.70  5307.4 1268.20  5324.6 1270.41
  5352.9 1270.20  5495.2 1278.24  5512.5 1277.94  5535.3 1280.21  5646.2 1284.19
#Mann=3,-1,0
  4218.3    0.05       0  4998.6    0.05       0  5012.4    0.05       0
Bank Sta=4998.6,5012.4
Exp/Cntr=0.3,0.1

Type RM Length L Ch R = 1,31500,500,500,500
BEGIN DESCRIPTION:
BENNETT CREEK 63.0
END DESCRIPTION:
XS GIS Cut Line= 3
      2774755.65     10203653.11      2775269.53     10203680.45
      2775655.66     10203353.13
#Sta/Elev= 30
  4485.4 1310.25  4545.5 1308.80  4565.5 1306.50  4575.0 1305.00  4605.6 1297.79
  4635.6 1292.91  4675.7 1285.28  4695.7 1280.48  4735.8 1273.52  4764.3 1270.40
  4769.3 1270.72  4845.9 1264.80  4926.1 1260.50  4958.5 1260.71  4979.6 1258.01
  4986.1 1256.46  4988.7 1254.47  4989.2 1253.97  5002.0 1253.97  5002.5 1254.47
  5023.4 1259.14  5031.1 1260.23  5045.4 1260.52  5059.7 1262.05  5094.8 1263.20
  5152.0 1263.74  5239.2 1266.98  5349.7 1272.73  5478.2 1282.33  5506.2 1283.71
#Mann=5,-1,0
  4485.4    0.05       0  4979.6    0.12       0  4988.7    0.07       0
  5002.5    0.12       0  5239.2    0.05       0
Bank Sta=4988.7,5002.5
Exp/Cntr=0.3,0.1

Type RM Length L Ch R = 1,31000,500,500,500
BEGIN DESCRIPTION:
BENNETT CREEK 62.0
END DESCRIPTION:
XS GIS Cut Line= 3
      2775005.68     10204053.11      2775517.42     10204108.16
      2775905.66     10203603.15
#Sta/Elev= 30
  4485.3 1281.90  4575.8 1277.84  4616.1 1274.42  4623.3 1273.02  4636.2 1273.44
  4686.5 1269.00  4736.8 1265.96  4904.4 1258.20  4958.0 1256.54  4978.1 1253.68
  4988.2 1253.49  4992.9 1252.64  4993.4 1252.14  5006.7 1252.64  5009.0 1255.26
  5017.2 1255.94  5023.5 1257.89  5058.9 1260.42  5094.7 1261.52  5107.7 1261.21
  5131.4 1261.59  5137.7 1260.95  5173.0 1261.10  5181.2 1260.35  5245.6 1260.44
  5359.7 1263.80  5467.6 1267.21  5531.4 1269.26  5579.9 1270.71  5637.0 1273.60
#Mann=7,-1,0
  4485.3    0.05       0  4992.9    0.05       0  5006.7    0.05       0
  5107.7    0.12       0  5359.7    0.05       0  5467.6    0.12       0
  5531.4    0.05       0
Bank Sta=4992.9,5006.7
Exp/Cntr=0.3,0.1

Type RM Length L Ch R = 1,30500,500,500,500
BEGIN DESCRIPTION:
BENNETT CREEK 61.0
END DESCRIPTION:
XS GIS Cut Line= 3
      2775405.65     10204803.14      2775773.03     10204531.50
      2776155.68     10204053.11
#Sta/Elev= 30
  4543.1 1271.12  4585.9 1269.32  4600.6 1269.55  4629.8 1268.42  4750.9 1266.03
  4829.2 1262.79  4892.8 1259.21  4907.4 1256.94  4951.3 1253.88  4972.1 1251.07
  4978.4 1249.69  4986.8 1250.06  4991.6 1248.89  4992.1 1248.39  5005.0 1248.39
  5005.5 1248.89  5014.7 1250.23  5022.7 1252.31  5029.1 1255.85  5036.4 1259.04
  5053.5 1259.07  5057.9 1259.17  5064.3 1258.36  5086.7 1258.87  5093.1 1257.79
  5118.7 1257.78  5164.4 1257.15  5299.6 1261.64  5427.7 1269.46  5612.6 1279.04
#Mann=5,-1,0
  4543.1    0.05       0  4991.6    0.03       0  5005.5    0.05       0
  5053.5    0.12       0  5118.7    0.05       0
Bank Sta=4991.6,5005.5
Exp/Cntr=0.3,0.1

Type RM Length L Ch R = 1,30000,500,500,500
BEGIN DESCRIPTION:
BENNETT CREEK 60.0
END DESCRIPTION:
XS GIS Cut Line= 3
      2775555.72     10205053.10      2776036.44     10204948.37
      2776455.68     10204603.12
#Sta/Elev= 30
  4508.0 1268.19  4630.8 1265.29  4682.0 1263.05  4712.7 1262.67  4804.8 1258.77
  4855.6 1255.80  4876.4 1255.57  4921.1 1256.55  4937.8 1256.34  4958.8 1253.10
  4968.5 1250.19  4978.8 1248.28  4982.0 1245.29  4982.5 1244.79  4995.4 1244.79
  4995.9 1245.29  4997.1 1247.09  5003.0 1247.97  5010.8 1247.99  5046.0 1256.33
  5060.3 1257.26  5066.8 1256.67  5081.1 1256.85  5089.0 1256.07  5095.5 1256.61
  5138.5 1255.40  5176.4 1255.67  5258.3 1259.65  5408.2 1263.57  5543.1 1269.03
#Mann=5,-1,0
  4508.0    0.05       0  4921.1    0.12       0  4982.0    0.07       0
  4995.9    0.12       0  5176.4    0.05       0
Bank Sta=4982,4995.9
Exp/Cntr=0.3,0.1

Type RM Length L Ch R = 1,29500,500,500,500
BEGIN DESCRIPTION:
BENNETT CREEK 59.0
END DESCRIPTION:
XS GIS Cut Line= 3
      2775855.69     10205753.10      2776349.31     10205332.06
      2777155.66     10205253.11
#Sta/Elev= 30
  4351.2 1267.52  4436.3 1265.34  4493.4 1261.90  4635.0 1256.49  4719.5 1254.52
  4883.2 1255.13  4932.6 1252.61  4940.3 1251.10  4946.8 1251.52  4973.8 1247.01
  4999.4 1245.17  4999.9 1244.67  5013.4 1245.17  5026.5 1246.97  5041.0 1251.32
  5046.6 1251.86  5066.7 1250.31  5106.9 1252.42  5137.0 1250.62  5187.4 1252.34
  5327.9 1254.09  5345.7 1252.10  5350.7 1253.42  5378.2 1250.56  5398.3 1249.80
  5447.2 1255.51  5452.3 1254.79  5548.8 1260.92  5559.0 1260.65  5810.2 1274.73
#Mann=5,-1,0
  4351.2    0.05       0  4973.8    0.12       0  4999.4    0.07       0
  5013.4    0.12       0  5187.4    0.05       0
Bank Sta=4999.4,5013.4
Exp/Cntr=0.3,0.1

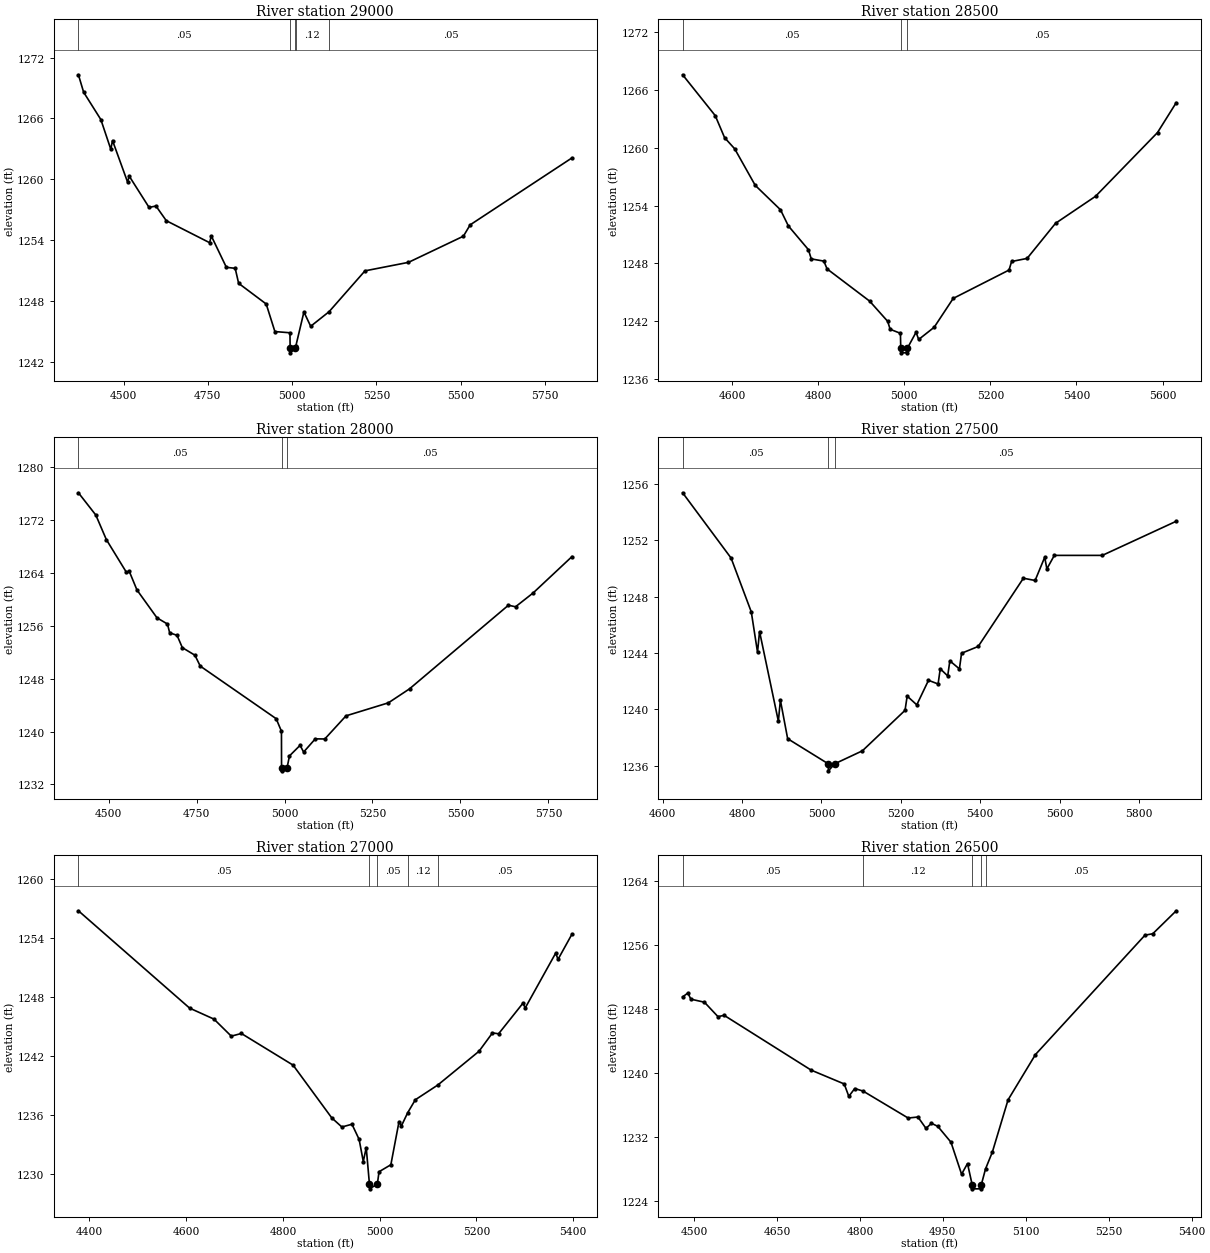
Type RM Length L Ch R = 1,29000,500,500,500
BEGIN DESCRIPTION:
BENNETT CREEK 58.0
END DESCRIPTION:
XS GIS Cut Line= 3
      2775810.56     10205908.80      2776430.84     10205777.63
      2777255.82     10205874.08
#Sta/Elev= 30
  4366.0 1270.30  4381.5 1268.58  4432.6 1265.88  4462.1 1262.95  4467.2 1263.81
  4511.8 1259.72  4516.9 1260.29  4575.7 1257.21  4596.1 1257.35  4626.8 1255.90
  4755.3 1253.73  4760.4 1254.39  4805.0 1251.30  4831.2 1251.20  4841.4 1249.72
  4923.2 1247.68  4949.0 1244.96  4993.7 1244.84  4994.2 1243.36  4994.7 1242.86
  5009.9 1243.36  5010.9 1243.50  5035.1 1246.89  5055.2 1245.48  5109.8 1246.92
  5216.3 1250.95  5345.4 1251.79  5508.3 1254.37  5528.4 1255.49  5830.6 1262.10
#Mann=5,-1,0
  4366.0    0.05       0  4994.2    0.05       0  5009.9    0.05       0
  5010.9    0.12       0  5109.8    0.05       0
Bank Sta=4994.2,5009.9
Exp/Cntr=0.3,0.1

Type RM Length L Ch R = 1,28500,500,500,500
BEGIN DESCRIPTION:
BENNETT CREEK 57.0
END DESCRIPTION:
XS GIS Cut Line= 3
      2775805.67     10206053.11      2776281.43     10206250.55
      2776805.70     10206603.12
#Sta/Elev= 30
  4484.9 1267.60  4560.7 1263.35  4582.4 1261.06  4605.9 1259.90  4653.6 1256.10
  4712.3 1253.56  4730.6 1251.88  4777.2 1249.41  4783.8 1248.45  4813.1 1248.22
  4820.5 1247.41  4919.4 1244.06  4961.3 1241.96  4967.1 1241.13  4991.0 1240.71
  4991.7 1239.18  4992.2 1238.68  5006.9 1238.68  5007.4 1239.18  5027.3 1240.82
  5033.4 1240.07  5069.4 1241.34  5113.6 1244.34  5243.3 1247.29  5249.3 1248.18
  5285.3 1248.50  5351.3 1252.15  5444.3 1254.96  5588.3 1261.59  5631.8 1264.70
#Mann=3,-1,0
  4484.9    0.05       0  4991.7    0.05       0  5007.4    0.05       0
Bank Sta=4991.7,5007.4
Exp/Cntr=0.3,0.1

Type RM Length L Ch R = 1,28000,500,500,500
BEGIN DESCRIPTION:
BENNETT CREEK 56.0
END DESCRIPTION:
XS GIS Cut Line= 3
      2775555.69     10206353.12      2776041.70     10206680.53
      2776855.67     10206753.11
#Sta/Elev= 30
  4414.0 1276.13  4463.5 1272.76  4493.4 1269.05  4550.4 1264.10  4558.7 1264.23
  4580.4 1261.43  4637.4 1257.21  4667.2 1256.27  4673.4 1254.95  4694.4 1254.56
  4709.4 1252.70  4745.3 1251.55  4760.3 1249.91  4976.2 1241.95  4991.2 1240.05
  4991.5 1234.56  4992.0 1234.06  5007.3 1234.56  5014.0 1236.32  5044.2 1237.92
  5054.2 1236.90  5087.4 1238.90  5114.4 1238.88  5174.7 1242.38  5295.2 1244.35
  5355.4 1246.47  5636.5 1259.12  5656.6 1258.88  5706.8 1260.98  5817.2 1266.48
#Mann=3,-1,0
  4414.0    0.05       0  4991.5    0.03       0  5007.3    0.05       0
Bank Sta=4991.5,5007.3
Exp/Cntr=0.3,0.1

Type RM Length L Ch R = 1,27500,500,500,500
BEGIN DESCRIPTION:
BENNETT CREEK 55.0
END DESCRIPTION:
XS GIS Cut Line= 3
      2775605.68     10207103.11      2775949.25     10207167.77
      2776778.44     10207501.70
#Sta/Elev= 30
  4650.4 1255.36  4772.5 1250.73  4823.4 1246.91  4839.1 1244.05  4844.2 1245.52
  4891.6 1239.16  4896.7 1240.65  4915.0 1237.92  5017.2 1236.14  5017.7 1235.64
  5033.6 1236.14  5103.3 1237.06  5210.7 1239.93  5216.1 1240.94  5240.3 1240.32
  5269.8 1242.06  5294.0 1241.80  5299.4 1242.88  5318.2 1242.37  5323.6 1243.44
  5347.7 1242.87  5353.1 1243.98  5395.0 1244.46  5508.9 1249.30  5538.4 1249.14
  5562.6 1250.79  5568.0 1249.96  5586.8 1250.92  5707.7 1250.92  5893.9 1253.34
#Mann=3,-1,0
  4650.4    0.05       0  5017.2    0.03       0  5033.6    0.05       0
Bank Sta=5017.2,5033.6
Exp/Cntr=0.3,0.1

Type RM Length L Ch R = 1,27000,500,500,500
BEGIN DESCRIPTION:
BENNETT CREEK 54.0
END DESCRIPTION:
XS GIS Cut Line= 3
      2775455.66     10207303.10      2775962.83     10207664.56
      2776355.66     10207603.12
#Sta/Elev= 30
  4377.2 1256.76  4607.1 1246.86  4657.5 1245.74  4693.2 1244.01  4714.1 1244.28
  4821.0 1241.06  4900.9 1235.70  4921.8 1234.77  4942.7 1235.05  4957.5 1233.51
  4966.1 1231.26  4972.2 1232.67  4978.8 1228.98  4979.3 1228.48  4995.2 1228.98
  4998.7 1230.22  5023.1 1230.93  5040.0 1235.32  5045.1 1234.90  5057.9 1236.22
  5073.7 1237.54  5120.2 1239.04  5205.3 1242.47  5233.2 1244.34  5245.8 1244.25
  5296.0 1247.35  5301.0 1246.89  5363.7 1252.44  5368.8 1251.83  5397.6 1254.39
#Mann=5,-1,0
  4377.2    0.05       0  4978.8    0.05       0  4995.2    0.05       0
  5057.9    0.12       0  5120.2    0.05       0
Bank Sta=4978.8,4995.2
Exp/Cntr=0.3,0.1

Type RM Length L Ch R = 1,26500,500,500,500
BEGIN DESCRIPTION:
BENNETT CREEK 53.0
END DESCRIPTION:
XS GIS Cut Line= 3
      2775505.69     10207553.13      2775694.60     10208038.14
      2775955.69     10208303.12
#Sta/Elev= 30
  4479.5 1249.47  4489.0 1249.96  4494.4 1249.19  4518.9 1248.81  4543.4 1247.01
  4554.6 1247.17  4711.9 1240.32  4771.7 1238.59  4780.0 1237.04  4790.7 1238.02
  4805.8 1237.70  4887.3 1234.33  4905.0 1234.46  4919.5 1233.04  4929.5 1233.67
  4940.9 1233.29  4964.7 1231.31  4983.9 1227.31  4994.6 1228.64  5003.1 1225.98
  5003.6 1225.48  5019.0 1225.48  5019.5 1225.98  5027.2 1227.97  5039.6 1230.09
  5067.9 1236.60  5117.5 1242.27  5315.5 1257.19  5329.6 1257.37  5372.0 1260.24
#Mann=5,-1,0
  4479.5    0.05       0  4805.8    0.12       0  5003.1    0.07       0
  5019.5    0.12       0  5027.2    0.05       0
Bank Sta=5003.1,5019.5
Exp/Cntr=0.3,0.1

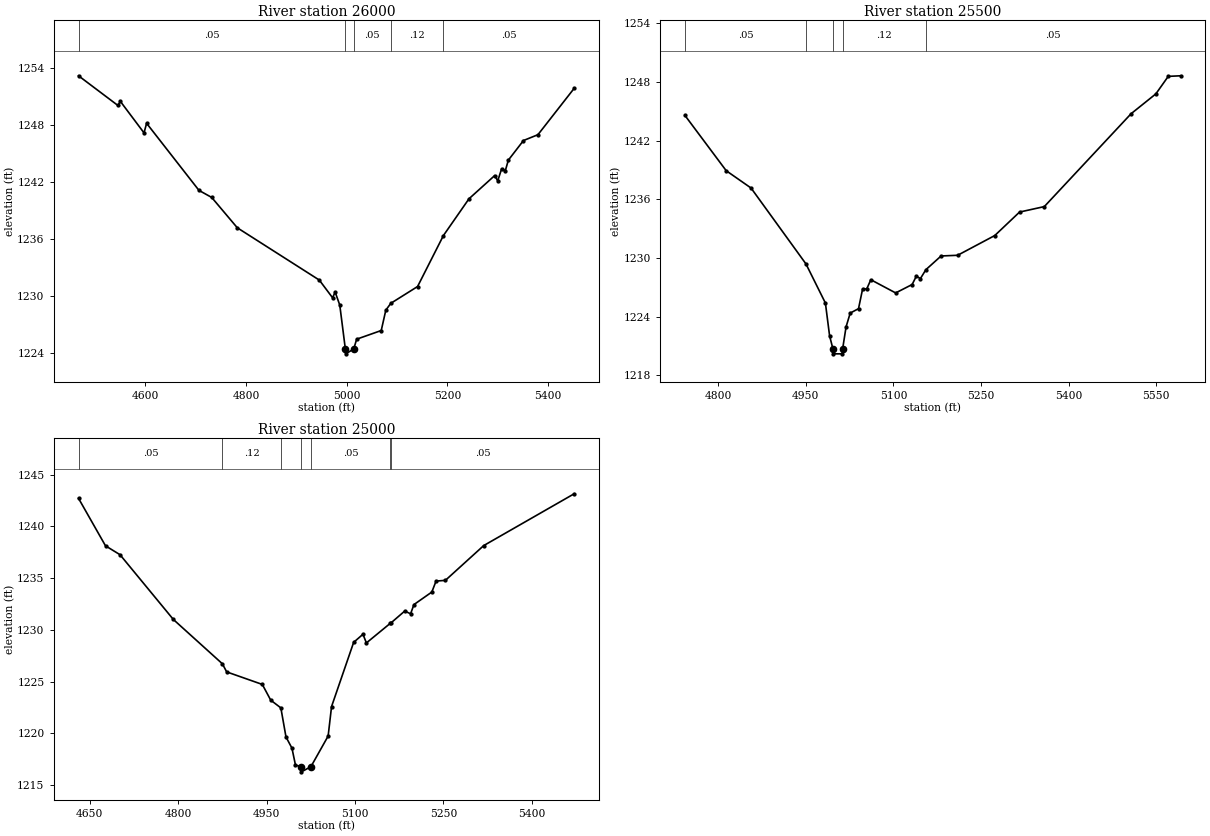
Type RM Length L Ch R = 1,26000,500,500,500
BEGIN DESCRIPTION:
BENNETT CREEK 52.0
END DESCRIPTION:
XS GIS Cut Line= 3
      2775305.68     10207553.11      2775205.58     10208076.63
      2775455.69     10208453.12
#Sta/Elev= 30
  4467.0 1253.16  4545.1 1250.05  4550.2 1250.47  4597.2 1247.16  4602.3 1248.17
  4706.4 1241.12  4731.7 1240.38  4782.6 1237.19  4945.5 1231.70  4971.9 1229.84
  4977.0 1230.44  4986.2 1229.07  4997.3 1224.45  4997.8 1223.95  5013.8 1224.45
  5019.8 1225.49  5068.6 1226.40  5077.7 1228.54  5087.7 1229.26  5140.8 1231.02
  5192.2 1236.38  5243.0 1240.24  5294.1 1242.68  5300.1 1242.12  5307.9 1243.40
  5315.2 1243.19  5321.2 1244.30  5351.3 1246.36  5380.0 1246.97  5452.0 1251.84
#Mann=5,-1,0
  4467.0    0.05       0  4997.3    0.05       0  5013.8    0.05       0
  5087.7    0.12       0  5192.2    0.05       0
Bank Sta=4997.3,5013.8
Exp/Cntr=0.3,0.1

Type RM Length L Ch R = 1,25500,500,500,500
BEGIN DESCRIPTION:
BENNETT CREEK 51.0
END DESCRIPTION:
XS GIS Cut Line= 3
      2774605.68     10208103.10      2774790.27     10208281.63
      2775205.69     10208703.12
#Sta/Elev= 30
  4743.2 1244.59  4813.8 1238.94  4856.3 1237.17  4950.3 1229.41  4983.6 1225.41
  4990.8 1222.05  4996.5 1220.71  4997.0 1220.21  5012.6 1220.21  5013.1 1220.71
  5019.0 1222.97  5026.1 1224.38  5040.3 1224.83  5047.3 1226.84  5054.4 1226.85
  5061.4 1227.79  5103.9 1226.44  5132.1 1227.30  5139.3 1228.15  5146.3 1227.91
  5155.7 1228.82  5181.7 1230.22  5210.0 1230.29  5273.6 1232.31  5316.0 1234.71
  5358.4 1235.27  5507.0 1244.77  5549.4 1246.80  5570.6 1248.59  5591.8 1248.65
#Mann=5,-1,0
  4743.2    0.05       0  4950.3    0.12       0  4996.5    0.07       0
  5013.1    0.12       0  5155.7    0.05       0
Bank Sta=4996.5,5013.1
Exp/Cntr=0.3,0.1

Type RM Length L Ch R = 1,25000,500,500,500
BEGIN DESCRIPTION:
BENNETT CREEK 50.0
END DESCRIPTION:
XS GIS Cut Line= 3
      2774455.69     10208253.14      2774495.37     10208620.00
      2774905.68     10208853.11
#Sta/Elev= 30
  4631.0 1242.71  4676.8 1238.12  4701.4 1237.26  4791.9 1231.00  4875.0 1226.72
  4882.4 1225.93  4942.8 1224.72  4957.1 1223.20  4974.3 1222.45  4983.0 1219.64
  4993.1 1218.56  4999.1 1216.92  5008.7 1216.77  5009.2 1216.27  5025.3 1216.77
  5054.5 1219.73  5060.3 1222.58  5097.8 1228.79  5113.6 1229.57  5119.4 1228.73
  5159.6 1230.61  5161.4 1230.68  5184.4 1231.81  5194.4 1231.55  5200.1 1232.44
  5230.4 1233.65  5237.6 1234.71  5253.4 1234.78  5318.4 1238.14  5471.9 1243.15
#Mann=7,-1,0
  4631.0    0.05       0  4875.0    0.12       0  4974.3    0.05       0
  5008.7    0.03       0  5025.3    0.05       0  5159.6    0.12       0
  5161.4    0.05       0
Bank Sta=5008.7,5025.3
Exp/Cntr=0.3,0.1