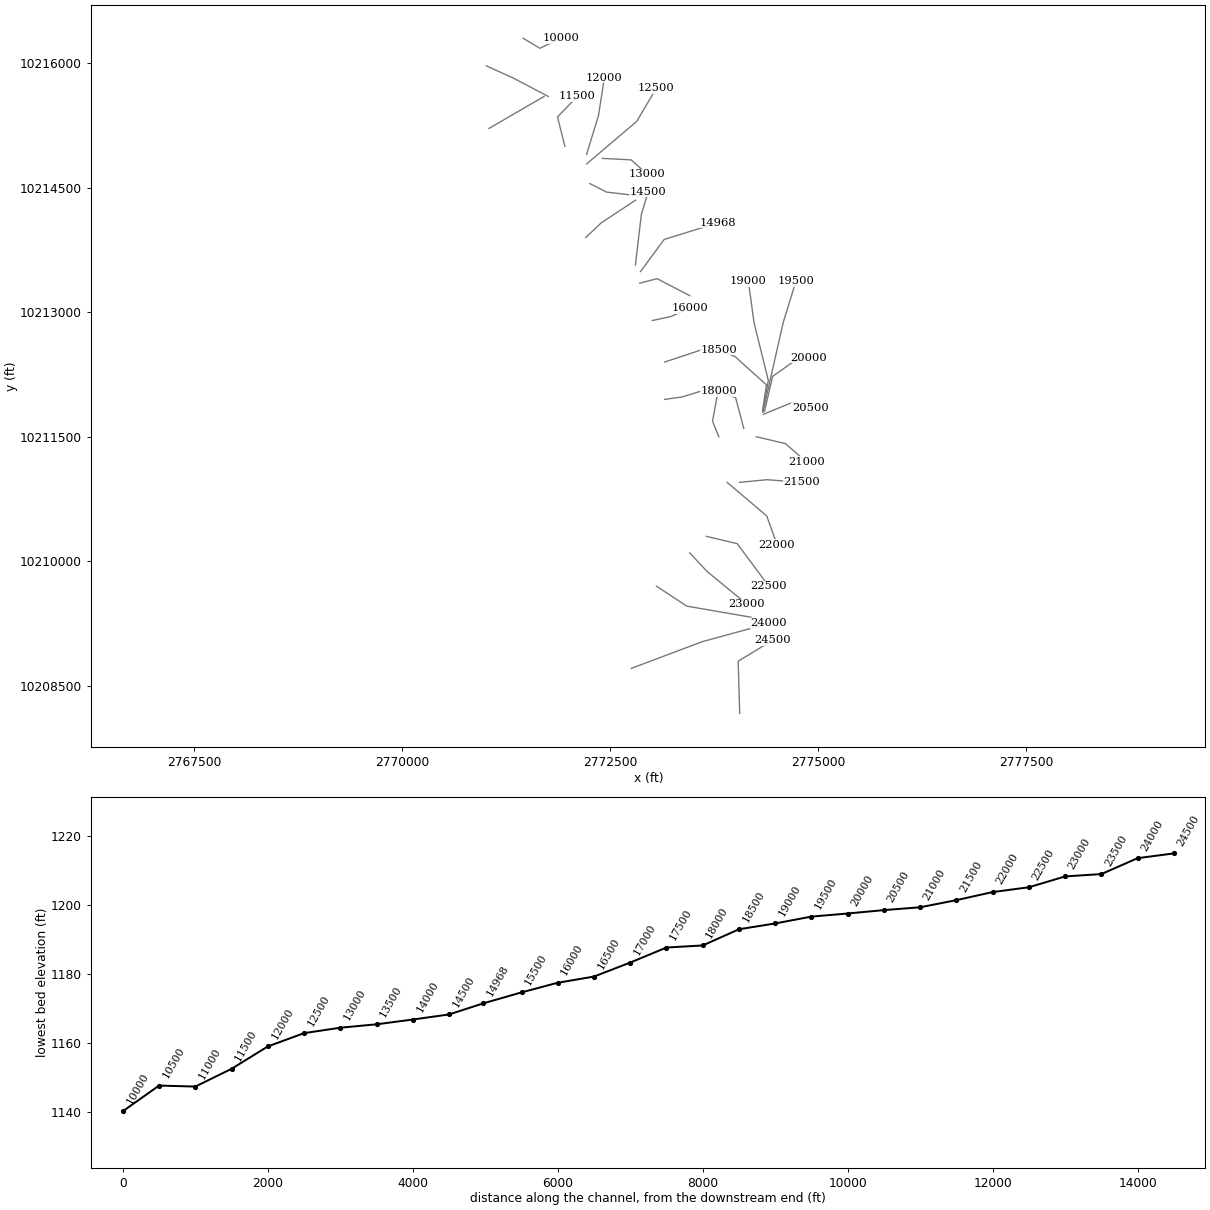
HEC-RAS study BENNETT CREEK.prj: BENNETT CREEK Base Level Engineering

--- BENNETT CREEK.g01 (geometry) --- (continued)

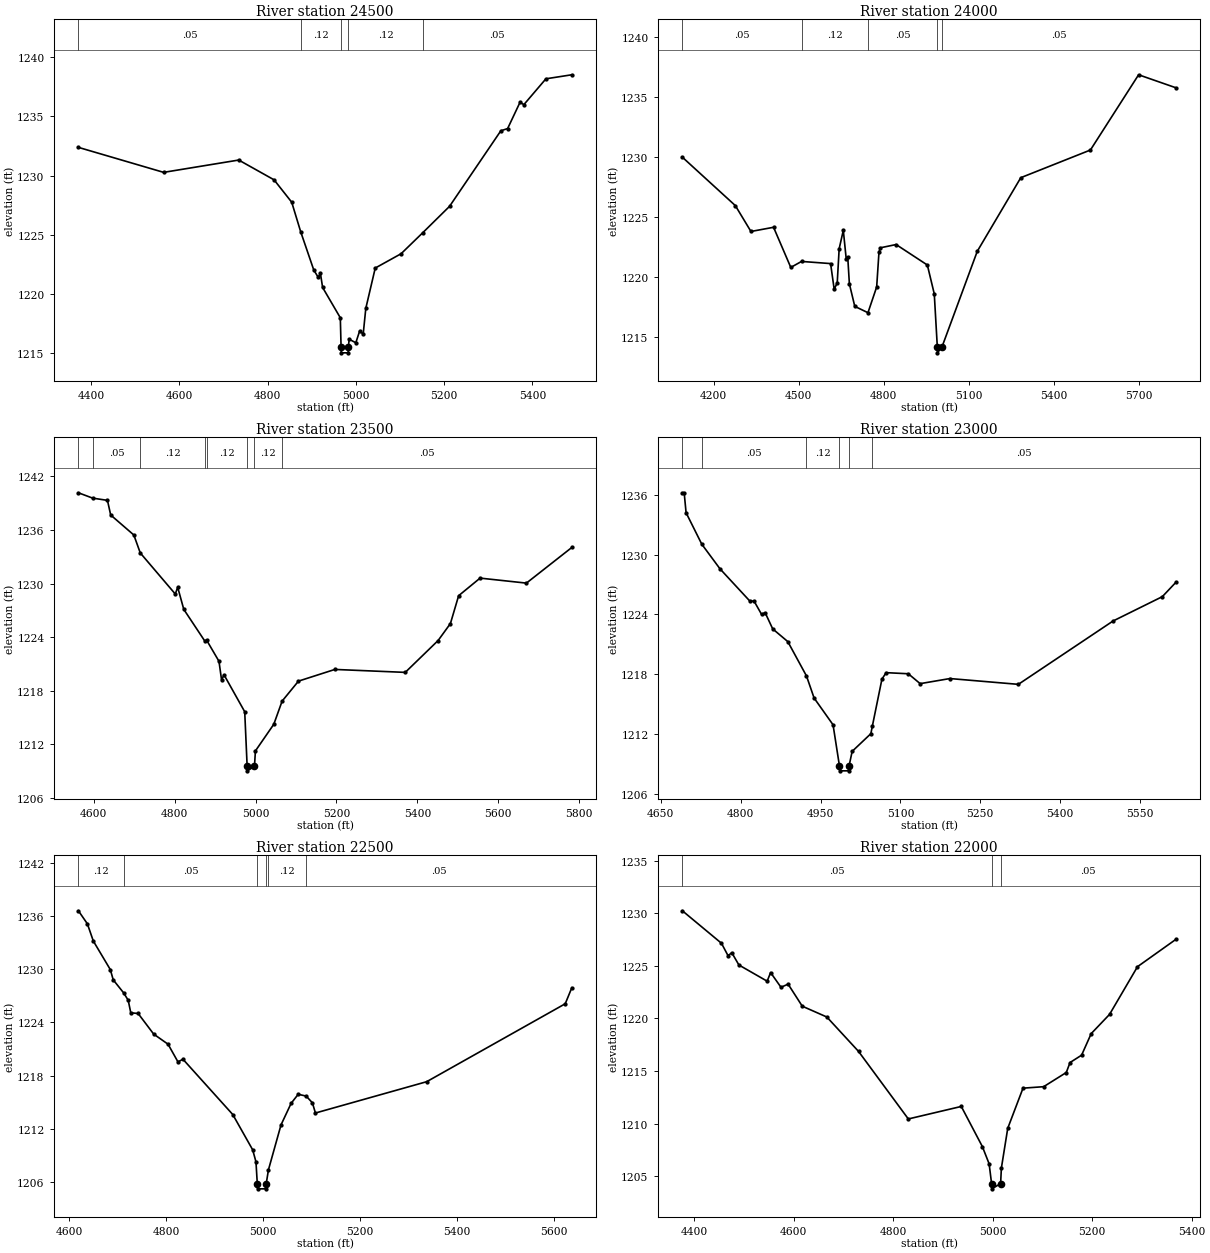
Type RM Length L Ch R = 1,24500,500,500,500
BEGIN DESCRIPTION:
BENNETT CREEK 49.0
END DESCRIPTION:
XS GIS Cut Line= 3
      2774057.05     10208170.12      2774038.28     10208798.44
      2774455.72     10209053.13
#Sta/Elev= 30
  4371.4 1232.38  4564.5 1230.27  4734.6 1231.31  4814.6 1229.64  4854.6 1227.75
  4874.8 1225.27  4904.6 1222.02  4914.6 1221.41  4919.6 1221.75  4924.6 1220.55
  4964.7 1217.99  4966.4 1215.53  4966.9 1215.03  4982.5 1215.03  4983.0 1215.53
  4984.7 1216.18  4999.8 1215.88  5008.7 1216.90  5016.5 1216.60  5022.4 1218.78
  5043.8 1222.19  5102.4 1223.40  5151.9 1225.19  5212.1 1227.40  5328.3 1233.78
  5343.7 1233.97  5371.8 1236.19  5380.5 1235.99  5430.4 1238.17  5489.0 1238.51
#Mann=5,-1,0
  4371.4    0.05       0  4874.8    0.12       0  4966.4    0.07       0
  4983.0    0.12       0  5151.9    0.05       0
Bank Sta=4966.4,4983
Exp/Cntr=0.3,0.1

Type RM Length L Ch R = 1,24000,500,500,500
BEGIN DESCRIPTION:
BENNETT CREEK 48.0
END DESCRIPTION:
XS GIS Cut Line= 3
      2772754.97     10208712.62      2773606.24     10209033.68
      2774405.67     10209253.11
#Sta/Elev= 30
  4090.2 1229.98  4276.9 1225.94  4331.9 1223.78  4411.6 1224.13  4472.3 1220.78
  4510.2 1221.28  4612.6 1221.10  4625.3 1218.95  4636.0 1219.50  4642.8 1222.34
  4657.4 1223.87  4667.6 1221.51  4673.0 1221.66  4678.8 1219.41  4697.8 1217.53
  4744.3 1217.00  4775.0 1219.15  4783.1 1222.05  4788.4 1222.42  4843.5 1222.69
  4953.6 1220.98  4978.0 1218.57  4988.7 1214.15  4989.2 1213.65  5005.3 1214.15
  5129.6 1222.13  5282.9 1228.27  5528.3 1230.58  5698.1 1236.86  5829.0 1235.78
#Mann=5,-1,0
  4090.2    0.05       0  4510.2    0.12       0  4744.3    0.05       0
  4988.7    0.05       0  5005.3    0.05       0
Bank Sta=4988.7,5005.3
Exp/Cntr=0.3,0.1

Type RM Length L Ch R = 1,23500,500,500,500
BEGIN DESCRIPTION:
BENNETT CREEK 47.0
END DESCRIPTION:
XS GIS Cut Line= 3
      2773055.70     10209703.10      2773421.11     10209462.14
      2774191.19     10209329.01
#Sta/Elev= 30
  4562.3 1240.17  4597.6 1239.57  4634.1 1239.32  4642.1 1237.68  4699.3 1235.44
  4715.2 1233.43  4801.7 1228.83  4807.7 1229.58  4822.7 1227.11  4874.5 1223.57
  4879.4 1223.64  4909.7 1221.29  4916.1 1219.20  4922.1 1219.78  4973.3 1215.64
  4979.3 1209.52  4979.8 1209.02  4997.4 1209.52  4999.7 1211.25  5045.2 1214.24
  5065.7 1216.83  5106.1 1219.07  5196.1 1220.38  5370.0 1220.05  5451.2 1223.62
  5481.6 1225.52  5501.9 1228.64  5554.9 1230.61  5669.4 1230.05  5781.5 1234.04
#Mann=8,-1,0
  4562.3    0.12       0  4597.6    0.05       0  4715.2    0.12       0
  4874.5    0.05       0  4879.4    0.12       0  4979.3    0.07       0
  4997.4    0.12       0  5065.7    0.05       0
Bank Sta=4979.3,4997.4
Exp/Cntr=0.3,0.1

Type RM Length L Ch R = 1,23000,500,500,500
BEGIN DESCRIPTION:
BENNETT CREEK 46.0
END DESCRIPTION:
XS GIS Cut Line= 3
      2773455.71     10210103.08      2773667.43     10209877.32
      2774143.89     10209485.16
#Sta/Elev= 30
  4690.5 1236.18  4693.9 1236.18  4697.5 1234.18  4727.0 1231.03  4761.1 1228.57
  4817.7 1225.31  4825.0 1225.35  4839.2 1224.01  4846.0 1224.17  4860.2 1222.55
  4888.5 1221.28  4923.6 1217.84  4937.9 1215.63  4973.5 1212.95  4985.5 1208.84
  4986.0 1208.34  5003.1 1208.34  5003.6 1208.84  5009.4 1210.29  5044.5 1212.06
  5047.4 1212.84  5065.3 1217.52  5073.2 1218.17  5114.8 1218.06  5137.1 1217.07
  5193.0 1217.58  5321.5 1217.00  5499.3 1223.34  5591.9 1225.78  5617.1 1227.20
#Mann=6,-1,0
  4690.5    0.12       0  4727.0    0.05       0  4923.6    0.12       0
  4985.5    0.07       0  5003.6    0.12       0  5047.4    0.05       0
Bank Sta=4985.5,5003.6
Exp/Cntr=0.3,0.1

Type RM Length L Ch R = 1,22500,500,500,500
BEGIN DESCRIPTION:
BENNETT CREEK 45.0
END DESCRIPTION:
XS GIS Cut Line= 3
      2773655.69     10210303.11      2774026.98     10210214.99
      2774405.66     10209703.15
#Sta/Elev= 30
  4618.4 1236.62  4636.9 1235.15  4649.2 1233.20  4684.3 1229.97  4690.3 1228.81
  4711.5 1227.36  4721.2 1226.51  4726.5 1225.09  4741.7 1225.01  4773.8 1222.68
  4803.4 1221.54  4823.9 1219.54  4834.2 1219.84  4937.0 1213.59  4978.1 1209.60
  4984.9 1208.24  4987.7 1205.69  4988.2 1205.19  5005.3 1205.19  5005.8 1205.69
  5010.7 1207.35  5036.6 1212.42  5057.5 1214.86  5072.1 1215.88  5088.6 1215.67
  5101.4 1214.91  5107.6 1213.76  5337.2 1217.30  5623.2 1226.11  5636.7 1227.91
#Mann=6,-1,0
  4618.4    0.12       0  4711.5    0.05       0  4987.7    0.05       0
  5005.8    0.05       0  5010.7    0.12       0  5088.6    0.05       0
Bank Sta=4987.7,5005.8
Exp/Cntr=0.3,0.1

Type RM Length L Ch R = 1,22000,500,500,500
BEGIN DESCRIPTION:
BENNETT CREEK 44.0
END DESCRIPTION:
XS GIS Cut Line= 3
      2773905.66     10210953.13      2774381.61     10210549.43
      2774505.69     10210203.08
#Sta/Elev= 30
  4375.9 1230.25  4454.5 1227.16  4467.7 1225.98  4475.3 1226.26  4489.6 1225.09
  4546.4 1223.55  4553.3 1224.37  4574.2 1222.97  4588.5 1223.27  4617.0 1221.17
  4666.4 1220.14  4730.1 1216.87  4830.2 1210.44  4936.7 1211.63  4979.1 1207.81
  4992.7 1206.17  4997.6 1204.29  4998.1 1203.79  5015.8 1204.29  5017.3 1205.76
  5030.1 1209.55  5060.8 1213.37  5102.3 1213.51  5147.8 1214.86  5155.4 1215.81
  5178.6 1216.51  5197.9 1218.56  5234.8 1220.39  5291.0 1224.93  5367.9 1227.52
#Mann=3,-1,0
  4375.9    0.05       0  4997.6    0.03       0  5015.8    0.05       0
Bank Sta=4997.6,5015.8
Exp/Cntr=0.3,0.1

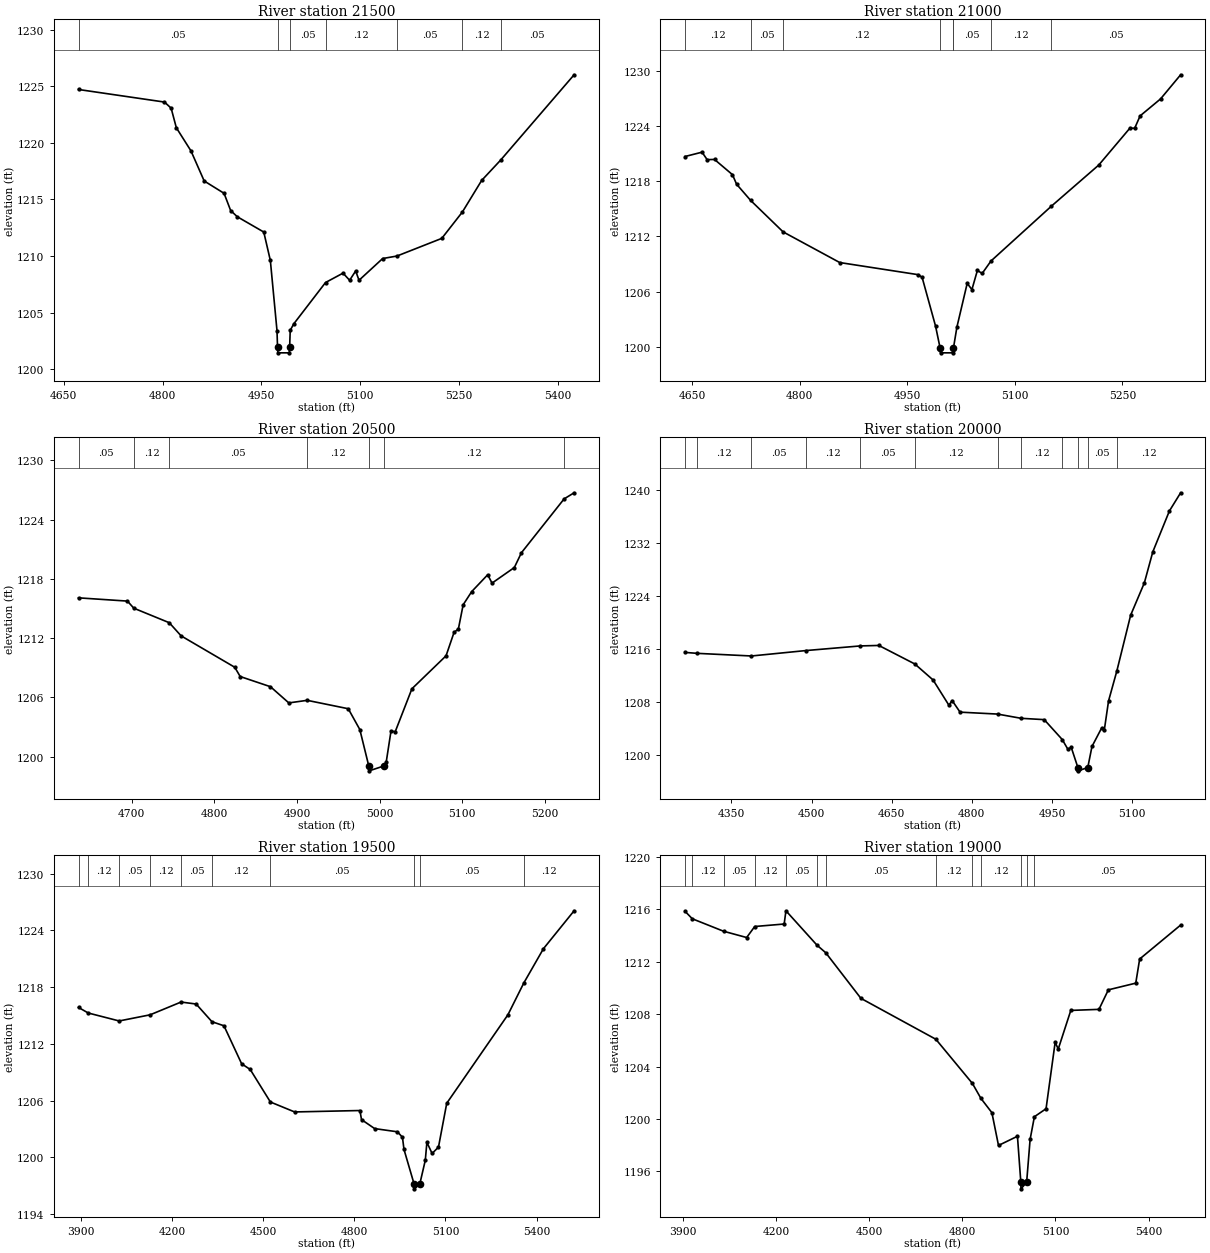
Type RM Length L Ch R = 1,21500,500,500,500
BEGIN DESCRIPTION:
BENNETT CREEK 43.0
END DESCRIPTION:
XS GIS Cut Line= 3
      2774055.71     10210953.11      2774381.70     10210985.56
      2774805.66     10210953.11
#Sta/Elev= 30
  4672.4 1224.71  4803.0 1223.60  4813.1 1223.06  4821.0 1221.33  4843.2 1219.29
  4863.3 1216.63  4893.5 1215.54  4903.5 1214.02  4913.6 1213.47  4953.8 1212.12
  4963.8 1209.61  4973.9 1203.41  4974.7 1201.95  4975.2 1201.45  4992.6 1201.45
  4993.1 1201.95  4994.0 1203.44  4999.5 1204.02  5047.6 1207.66  5074.2 1208.49
  5084.2 1207.86  5093.4 1208.68  5098.5 1207.86  5134.4 1209.78  5156.1 1210.00
  5224.2 1211.56  5255.5 1213.89  5284.8 1216.68  5313.4 1218.46  5425.2 1226.01
#Mann=7,-1,0
  4672.4    0.05       0  4974.7    0.03       0  4993.1    0.05       0
  5047.6    0.12       0  5156.1    0.05       0  5255.5    0.12       0
  5313.4    0.05       0
Bank Sta=4974.7,4993.1
Exp/Cntr=0.3,0.1

Type RM Length L Ch R = 1,21000,500,500,500
BEGIN DESCRIPTION:
BENNETT CREEK 42.0
END DESCRIPTION:
XS GIS Cut Line= 3
      2774255.69     10211503.11      2774605.92     10211420.66
      2774855.66     10211203.13
#Sta/Elev= 30
  4640.2 1220.68  4663.9 1221.15  4671.0 1220.34  4681.3 1220.36  4706.3 1218.71
  4712.1 1217.67  4731.7 1215.91  4776.9 1212.50  4855.9 1209.17  4965.6 1207.85
  4970.8 1207.55  4989.5 1202.27  4995.9 1199.87  4996.4 1199.37  5013.9 1199.37
  5014.4 1199.87  5014.5 1199.92  5019.3 1202.18  5033.6 1206.91  5040.2 1206.24
  5047.8 1208.31  5054.5 1207.99  5066.8 1209.34  5151.0 1215.29  5217.0 1219.75
  5260.5 1223.76  5267.1 1223.74  5274.7 1225.09  5303.2 1226.93  5331.2 1229.55
#Mann=8,-1,0
  4640.2    0.12       0  4731.7    0.05       0  4776.9    0.12       0
  4995.9    0.07       0  5014.4    0.12       0  5014.5    0.05       0
  5066.8    0.12       0  5151.0    0.05       0
Bank Sta=4995.9,5014.4
Exp/Cntr=0.3,0.1

Type RM Length L Ch R = 1,20500,500,500,500
BEGIN DESCRIPTION:
BENNETT CREEK 41.0
END DESCRIPTION:
XS GIS Cut Line= 3
      2774340.88     10211773.37      2774677.80     10211911.65
      2774905.70     10211853.11
#Sta/Elev= 30
  4635.8 1216.07  4695.0 1215.74  4702.7 1215.02  4745.6 1213.55  4759.9 1212.22
  4824.8 1209.04  4831.4 1208.10  4868.0 1207.07  4890.2 1205.43  4912.4 1205.69
  4962.1 1204.84  4976.1 1202.73  4986.9 1199.05  4987.4 1198.55  5005.4 1199.05
  5008.1 1199.48  5013.8 1202.58  5018.9 1202.51  5039.1 1206.86  5080.4 1210.20
  5090.1 1212.58  5095.3 1212.91  5101.1 1215.37  5111.4 1216.70  5130.8 1218.41
  5136.0 1217.56  5163.0 1219.14  5171.6 1220.64  5223.2 1226.09  5235.3 1226.71
#Mann=7,-1,0
  4635.8    0.05       0  4702.7    0.12       0  4745.6    0.05       0
  4912.4    0.12       0  4986.9    0.07       0  5005.4    0.12       0
  5223.2    0.05       0
Bank Sta=4986.9,5005.4
Exp/Cntr=0.3,0.1

Type RM Length L Ch R = 1,20000,500,500,500
BEGIN DESCRIPTION:
BENNETT CREEK 40.0
END DESCRIPTION:
XS GIS Cut Line= 4
      2774355.01     10211809.79      2774452.85     10212230.48
      2774701.66     10212406.51      2774886.02     10212455.67
#Sta/Elev= 30
  4263.3 1215.44  4285.7 1215.30  4387.6 1214.90  4489.6 1215.72  4591.5 1216.42
  4626.0 1216.49  4693.4 1213.69  4727.5 1211.28  4757.1 1207.47  4763.2 1208.17
  4778.0 1206.42  4848.1 1206.13  4892.3 1205.49  4935.5 1205.29  4969.2 1202.29
  4979.9 1200.80  4986.0 1201.12  4998.5 1198.06  4999.0 1197.56  5017.0 1198.06
  5024.9 1201.24  5042.7 1203.99  5047.9 1203.69  5055.9 1208.12  5071.3 1212.60
  5097.3 1221.07  5122.9 1225.94  5138.7 1230.62  5169.8 1236.80  5190.8 1239.54
#Mann=12,-1,0
  4263.3    0.05       0  4285.7    0.12       0  4387.6    0.05       0
  4489.6    0.12       0  4591.5    0.05       0  4693.4    0.12       0
  4848.1    0.05       0  4892.3    0.12       0  4969.2    0.05       0
  4998.5    0.05       0  5017.0    0.05       0  5071.3    0.12       0
Bank Sta=4998.5,5017
Exp/Cntr=0.3,0.1

Type RM Length L Ch R = 1,19500,500,500,500
BEGIN DESCRIPTION:
BENNETT CREEK 39.0
END DESCRIPTION:
XS GIS Cut Line= 3
      2774335.63     10211799.59      2774579.58     10212879.38
      2774733.91     10213379.51
#Sta/Elev= 30
  3893.0 1215.84  3925.1 1215.25  4026.8 1214.41  4128.6 1215.06  4230.3 1216.41
  4280.0 1216.20  4332.0 1214.33  4371.5 1213.90  4429.7 1209.88  4457.9 1209.28
  4524.3 1205.84  4604.0 1204.79  4818.8 1204.94  4824.0 1203.98  4867.2 1203.03
  4942.3 1202.69  4958.7 1202.11  4963.8 1200.82  4997.1 1197.16  4997.6 1196.66
  5015.7 1197.16  5033.9 1199.69  5039.1 1201.58  5056.2 1200.40  5077.2 1201.07
  5104.4 1205.71  5305.6 1215.06  5358.0 1218.43  5422.5 1222.05  5523.4 1226.06
#Mann=10,-1,0
  3893.0    0.05       0  3925.1    0.12       0  4026.8    0.05       0
  4128.6    0.12       0  4230.3    0.05       0  4332.0    0.12       0
  4524.3    0.05       0  4997.1    0.05       0  5015.7    0.05       0
  5358.0    0.12       0
Bank Sta=4997.1,5015.7
Exp/Cntr=0.3,0.1

Type RM Length L Ch R = 1,19000,500,500,500
BEGIN DESCRIPTION:
BENNETT CREEK 38.0
END DESCRIPTION:
XS GIS Cut Line= 4
      2774333.27     10211807.62      2774400.67     10212181.57
      2774229.56     10212875.09      2774161.43     10213373.96
#Sta/Elev= 30
  3905.7 1215.84  3929.1 1215.27  4029.8 1214.32  4104.3 1213.84  4130.4 1214.68
  4225.3 1214.87  4231.0 1215.88  4331.4 1213.25  4359.3 1212.68  4472.7 1209.20
  4714.3 1206.08  4832.2 1202.71  4859.6 1201.57  4895.0 1200.48  4916.3 1197.98
  4977.4 1198.68  4988.3 1195.17  4988.8 1194.67  5007.0 1195.17  5018.2 1198.44
  5032.0 1200.17  5069.6 1200.78  5098.9 1205.84  5109.0 1205.34  5149.4 1208.28
  5240.2 1208.36  5270.5 1209.85  5358.8 1210.36  5371.4 1212.20  5503.5 1214.79
#Mann=13,-1,0
  3905.7    0.05       0  3929.1    0.12       0  4029.8    0.05       0
  4130.4    0.12       0  4231.0    0.05       0  4331.4    0.12       0
  4359.3    0.05       0  4714.3    0.12       0  4832.2    0.05       0
  4859.6    0.12       0  4988.3    0.07       0  5007.0    0.12       0
  5032.0    0.05       0
Bank Sta=4988.3,5007
Exp/Cntr=0.3,0.1

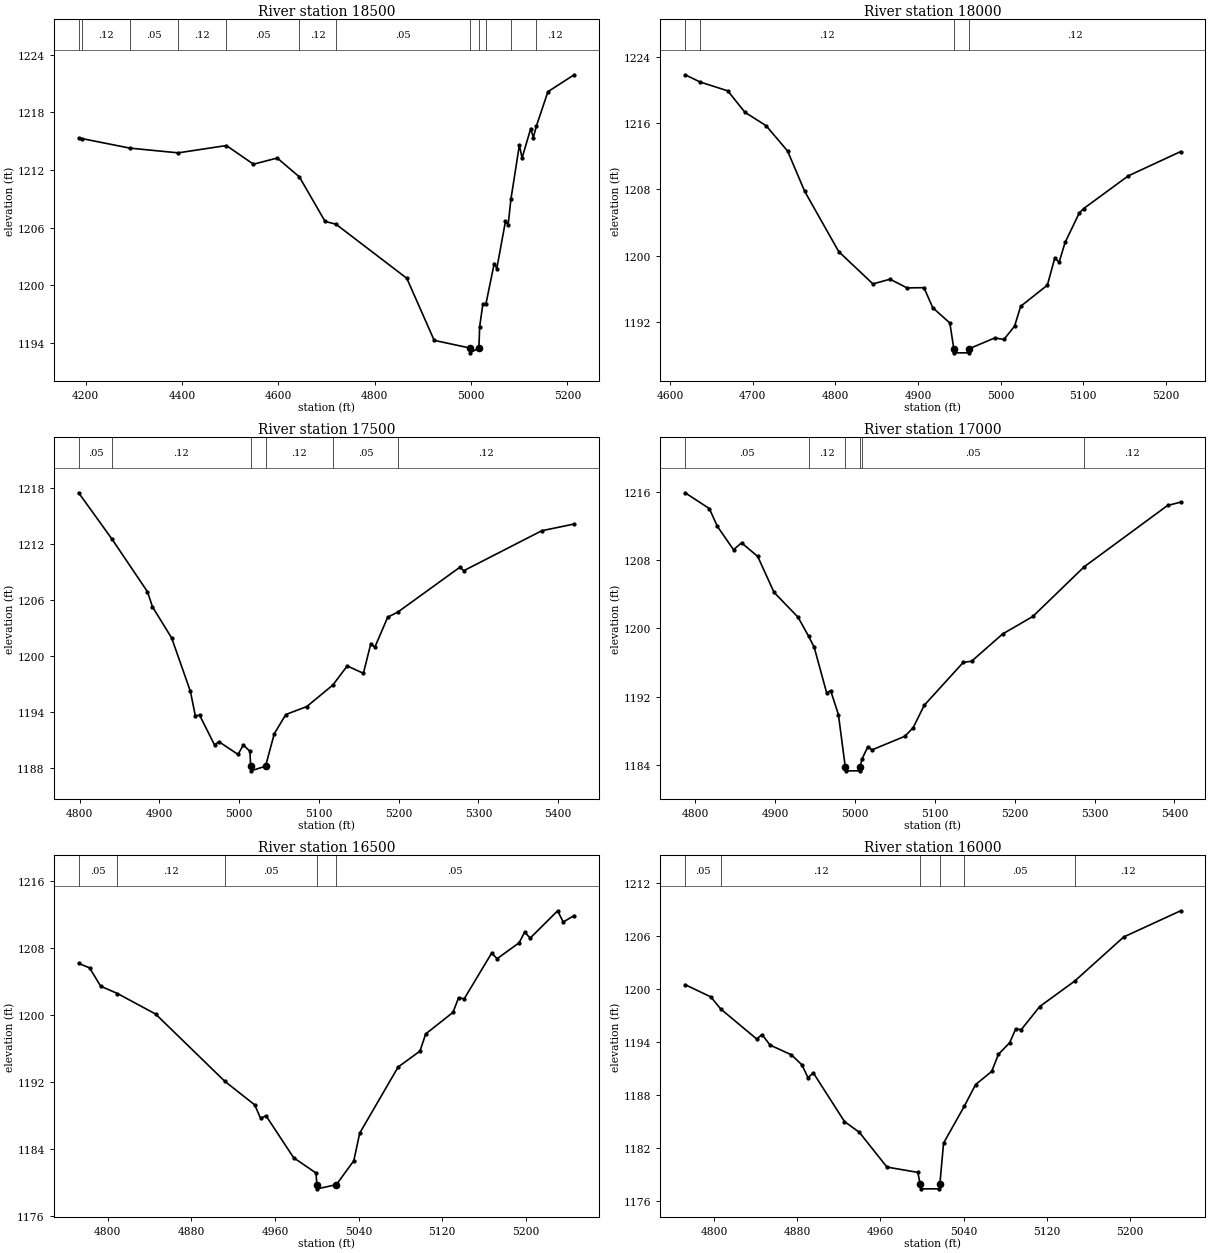
Type RM Length L Ch R = 1,18500,500,500,500
BEGIN DESCRIPTION:
BENNETT CREEK 37.0
END DESCRIPTION:
XS GIS Cut Line= 4
      2774332.19     10211824.11      2774378.87     10212127.33
      2774001.99     10212467.81      2773805.72     10212553.10
#Sta/Elev= 30
  4185.3 1215.28  4191.7 1215.27  4291.8 1214.27  4391.9 1213.78  4492.0 1214.54
  4548.2 1212.60  4597.6 1213.24  4643.5 1211.28  4696.9 1206.65  4719.5 1206.36
  4866.6 1200.73  4923.4 1194.28  4997.5 1193.48  4998.0 1192.98  5016.2 1193.48
  5017.8 1195.70  5024.5 1198.08  5031.0 1198.11  5048.0 1202.27  5053.4 1201.75
  5071.4 1206.67  5076.9 1206.29  5082.7 1208.96  5100.3 1214.60  5105.8 1213.24
  5123.8 1216.31  5129.2 1215.37  5135.6 1216.57  5159.5 1220.14  5214.0 1221.90
#Mann=12,-1,0
  4185.3    0.05       0  4191.7    0.12       0  4291.8    0.05       0
  4391.9    0.12       0  4492.0    0.05       0  4643.5    0.12       0
  4719.5    0.05       0  4997.5    0.05       0  5016.2    0.05       0
  5031.0    0.12       0  5082.7    0.05       0  5135.6    0.12       0
Bank Sta=4997.5,5016.2
Exp/Cntr=0.3,0.1

Type RM Length L Ch R = 1,18000,500,500,500
BEGIN DESCRIPTION:
BENNETT CREEK 36.0
END DESCRIPTION:
XS GIS Cut Line= 3
      2774105.68     10211603.14      2774008.32     10211972.53
      2773805.66     10212053.12
#Sta/Elev= 30
  4618.0 1221.80  4636.2 1220.93  4669.7 1219.86  4690.4 1217.28  4716.1 1215.66
  4742.1 1212.61  4762.8 1207.75  4804.1 1200.47  4845.5 1196.58  4866.2 1197.15
  4886.8 1196.10  4907.3 1196.13  4917.9 1193.71  4938.6 1191.87  4943.4 1188.77
  4943.9 1188.27  4961.6 1188.27  4962.1 1188.77  4993.1 1190.07  5004.1 1189.88
  5017.0 1191.49  5024.4 1193.88  5056.7 1196.43  5065.6 1199.67  5071.0 1199.22
  5078.2 1201.58  5095.3 1205.13  5100.7 1205.67  5154.7 1209.61  5218.1 1212.54
#Mann=4,-1,0
  4618.0    0.05       0  4636.2    0.12       0  4943.4    0.07       0
  4962.1    0.12       0
Bank Sta=4943.4,4962.1
Exp/Cntr=0.3,0.1

Type RM Length L Ch R = 1,17500,500,500,500
BEGIN DESCRIPTION:
BENNETT CREEK 35.0
END DESCRIPTION:
XS GIS Cut Line= 3
      2773805.68     10211503.12      2773730.35     10211689.79
      2773805.68     10212103.08
#Sta/Elev= 30
  4798.7 1217.49  4840.8 1212.49  4885.0 1206.88  4891.3 1205.26  4915.4 1201.91
  4938.9 1196.18  4945.0 1193.58  4950.4 1193.64  4969.1 1190.45  4974.5 1190.80
  4998.6 1189.43  5005.2 1190.44  5013.5 1189.77  5014.4 1188.17  5014.9 1187.67
  5033.1 1188.17  5044.0 1191.64  5058.5 1193.71  5084.7 1194.56  5117.5 1196.87
  5135.5 1198.92  5155.8 1198.13  5165.1 1201.31  5170.1 1200.92  5186.3 1204.15
  5199.2 1204.71  5276.7 1209.50  5281.8 1209.14  5379.5 1213.42  5420.1 1214.14
#Mann=6,-1,0
  4798.7    0.05       0  4840.8    0.12       0  5014.4    0.07       0
  5033.1    0.12       0  5117.5    0.05       0  5199.2    0.12       0
Bank Sta=5014.4,5033.1
Exp/Cntr=0.3,0.1

Type RM Length L Ch R = 1,17000,500,500,500
BEGIN DESCRIPTION:
BENNETT CREEK 34.0
END DESCRIPTION:
XS GIS Cut Line= 3
      2773155.72     10211953.12      2773366.00     10211983.02
      2773755.71     10212103.12
#Sta/Elev= 30
  4787.6 1215.92  4817.9 1214.07  4828.0 1211.98  4848.2 1209.24  4858.3 1210.05
  4878.5 1208.45  4898.9 1204.24  4929.0 1201.32  4942.3 1199.07  4949.2 1197.79
  4964.7 1192.47  4969.8 1192.71  4979.5 1189.89  4988.0 1183.80  4988.5 1183.30
  5006.2 1183.30  5006.7 1183.80  5008.9 1184.66  5016.3 1186.13  5021.6 1185.76
  5062.5 1187.35  5072.9 1188.34  5086.9 1190.99  5135.7 1196.02  5146.2 1196.16
  5184.9 1199.35  5222.8 1201.41  5287.0 1207.23  5391.4 1214.43  5407.8 1214.82
#Mann=6,-1,0
  4787.6    0.05       0  4942.3    0.12       0  4988.0    0.07       0
  5006.7    0.12       0  5008.9    0.05       0  5287.0    0.12       0
Bank Sta=4988,5006.7
Exp/Cntr=0.3,0.1

Type RM Length L Ch R = 1,16500,500,500,500
BEGIN DESCRIPTION:
BENNETT CREEK 33.0
END DESCRIPTION:
XS GIS Cut Line= 3
      2773155.73     10212403.13      2773372.00     10212474.99
      2773605.69     10212553.11
#Sta/Elev= 30
  4772.1 1206.13  4782.6 1205.59  4793.2 1203.40  4809.3 1202.53  4845.8 1200.08
  4911.9 1192.07  4940.7 1189.24  4946.2 1187.65  4951.5 1187.94  4977.9 1182.94
  4999.3 1181.12  5000.1 1179.73  5000.6 1179.23  5018.8 1179.73  5035.5 1182.59
  5041.1 1185.87  5077.9 1193.76  5098.8 1195.66  5104.3 1197.71  5130.4 1200.28
  5135.8 1202.04  5141.1 1201.89  5167.4 1207.35  5172.7 1206.69  5193.7 1208.58
  5199.0 1209.85  5204.3 1209.14  5230.6 1212.40  5235.9 1211.06  5246.4 1211.83
#Mann=5,-1,0
  4772.1    0.05       0  4809.3    0.12       0  4911.9    0.05       0
  5000.1    0.05       0  5018.8    0.05       0
Bank Sta=5000.1,5018.8
Exp/Cntr=0.3,0.1

Type RM Length L Ch R = 1,16000,500,500,500
BEGIN DESCRIPTION:
BENNETT CREEK 32.0
END DESCRIPTION:
XS GIS Cut Line= 3
      2773005.68     10212903.11      2773228.59     10212951.01
      2773455.69     10213053.12
#Sta/Elev= 30
  4772.0 1200.51  4796.7 1199.13  4806.3 1197.76  4840.9 1194.37  4846.1 1194.87
  4853.8 1193.68  4874.3 1192.58  4884.5 1191.44  4890.3 1189.99  4895.4 1190.54
  4925.4 1185.04  4939.7 1183.82  4966.3 1179.89  4996.0 1179.29  4998.4 1177.93
  4998.9 1177.43  5016.7 1177.43  5017.2 1177.93  5020.8 1182.60  5040.8 1186.78
  5051.6 1189.21  5067.1 1190.70  5073.6 1192.63  5084.5 1193.96  5090.2 1195.49
  5095.7 1195.44  5113.4 1198.04  5147.0 1200.91  5194.2 1205.90  5249.0 1208.86
#Mann=6,-1,0
  4772.0    0.05       0  4806.3    0.12       0  4998.4    0.07       0
  5017.2    0.12       0  5040.8    0.05       0  5147.0    0.12       0
Bank Sta=4998.4,5017.2
Exp/Cntr=0.3,0.1

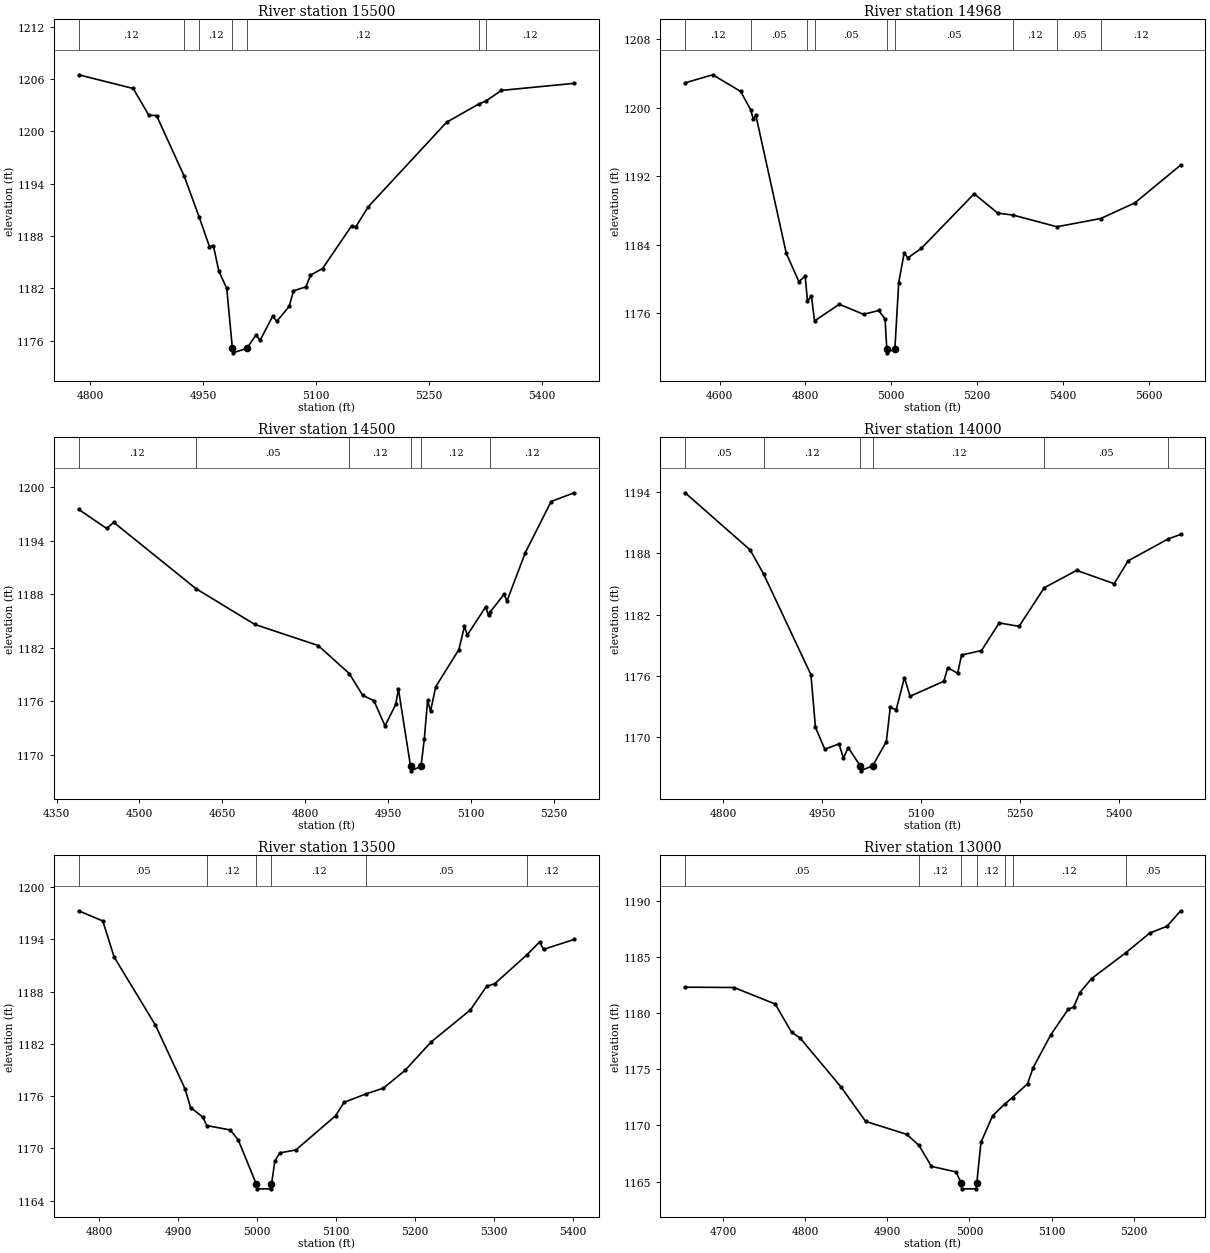
Type RM Length L Ch R = 1,15500,532,532,532
BEGIN DESCRIPTION:
BENNETT CREEK 31.0
END DESCRIPTION:
XS GIS Cut Line= 3
      2772855.70     10213353.12      2773063.60     10213407.92
      2773455.73     10213203.09
#Sta/Elev= 30
  4785.0 1206.48  4857.4 1204.91  4878.0 1201.86  4888.4 1201.80  4925.1 1194.86
  4944.9 1190.18  4958.6 1186.80  4963.7 1186.92  4971.1 1183.97  4981.5 1182.01
  4989.0 1175.13  4989.5 1174.63  5007.9 1175.13  5020.2 1176.66  5025.9 1176.09
  5042.3 1178.81  5048.0 1178.25  5064.4 1179.96  5070.0 1181.73  5086.5 1182.19
  5092.6 1183.53  5108.6 1184.29  5147.1 1189.17  5152.7 1189.06  5169.2 1191.36
  5273.1 1201.04  5315.6 1203.12  5325.3 1203.47  5345.8 1204.69  5442.4 1205.50
#Mann=7,-1,0
  4785.0    0.12       0  4925.1    0.05       0  4944.9    0.12       0
  4989.0    0.07       0  5007.9    0.12       0  5315.6    0.05       0
  5325.3    0.12       0
Bank Sta=4989,5007.9
Exp/Cntr=0.3,0.1

Type RM Length L Ch R = 1,14968,468,468,468
BEGIN DESCRIPTION:
BENNETT CREEK 30.0
END DESCRIPTION:
XS GIS Cut Line= 3
      2772864.70     10213493.31      2773149.25     10213880.00
      2773792.43     10214079.80
#Sta/Elev= 30
  4519.9 1202.91  4584.3 1203.85  4649.1 1201.91  4672.4 1199.79  4678.3 1198.74
  4684.6 1199.12  4755.5 1183.01  4784.8 1179.72  4799.5 1180.36  4804.8 1177.46
  4814.1 1178.03  4821.2 1175.13  4878.9 1177.08  4935.3 1175.90  4970.7 1176.35
  4985.4 1175.35  4989.4 1171.91  4989.9 1171.41  5008.3 1171.91  5017.2 1179.61
  5030.1 1183.10  5038.2 1182.48  5069.6 1183.59  5192.9 1189.97  5247.6 1187.71
  5283.5 1187.48  5385.5 1186.12  5487.5 1187.08  5566.8 1188.90  5673.5 1193.31
#Mann=9,-1,0
  4519.9    0.12       0  4672.4    0.05       0  4804.8    0.12       0
  4821.2    0.05       0  4989.4    0.05       0  5008.3    0.05       0
  5283.5    0.12       0  5385.5    0.05       0  5487.5    0.12       0
Bank Sta=4989.4,5008.3
Exp/Cntr=0.3,0.1

Type RM Length L Ch R = 1,14500,500,500,500
BEGIN DESCRIPTION:
BENNETT CREEK 29.0
END DESCRIPTION:
XS GIS Cut Line= 3
      2772803.56     10213572.78      2772874.45     10214178.64
      2772955.67     10214453.08
#Sta/Elev= 30
  4390.0 1197.53  4440.7 1195.39  4453.5 1196.07  4602.2 1188.64  4708.5 1184.63
  4823.3 1182.26  4879.4 1179.12  4903.8 1176.67  4924.0 1176.08  4944.1 1173.25
  4963.4 1175.65  4968.4 1177.36  4990.3 1168.71  4990.8 1168.21  5009.2 1168.71
  5015.1 1171.75  5021.1 1176.10  5026.4 1174.90  5035.9 1177.65  5077.7 1181.81
  5087.7 1184.40  5092.9 1183.43  5126.1 1186.59  5131.3 1185.64  5134.5 1186.04
  5159.4 1188.01  5164.6 1187.25  5197.9 1192.68  5244.5 1198.41  5286.2 1199.39
#Mann=6,-1,0
  4390.0    0.12       0  4602.2    0.05       0  4879.4    0.12       0
  4990.3    0.05       0  5009.2    0.12       0  5134.5    0.12       0
Bank Sta=4990.3,5009.2
Exp/Cntr=0.3,0.1

Type RM Length L Ch R = 1,14000,500,500,500
BEGIN DESCRIPTION:
BENNETT CREEK 28.0
END DESCRIPTION:
XS GIS Cut Line= 3
      2772205.70     10213903.12      2772393.25     10214080.72
      2772805.72     10214353.13
#Sta/Elev= 30
  4741.7 1193.90  4840.6 1188.31  4860.9 1185.97  4932.8 1176.13  4939.7 1170.98
  4953.9 1168.85  4975.3 1169.37  4982.2 1167.99  4989.4 1169.01  5007.6 1167.24
  5008.1 1166.74  5026.6 1167.24  5047.3 1169.59  5053.3 1172.93  5062.3 1172.71
  5074.8 1175.85  5083.4 1174.02  5134.6 1175.49  5140.6 1176.82  5155.6 1176.27
  5161.6 1178.05  5191.8 1178.49  5218.8 1181.19  5248.9 1180.85  5287.1 1184.62
  5336.3 1186.32  5393.4 1185.02  5414.5 1187.25  5475.6 1189.40  5494.3 1189.83
#Mann=6,-1,0
  4741.7    0.05       0  4860.9    0.12       0  5007.6    0.07       0
  5026.6    0.12       0  5287.1    0.05       0  5475.6    0.12       0
Bank Sta=5007.6,5026.6
Exp/Cntr=0.3,0.1

Type RM Length L Ch R = 1,13500,500,500,500
BEGIN DESCRIPTION:
BENNETT CREEK 27.0
END DESCRIPTION:
XS GIS Cut Line= 3
      2772255.64     10214553.13      2772456.84     10214450.64
      2772855.72     10214403.11
#Sta/Elev= 30
  4774.2 1197.27  4804.8 1196.10  4819.1 1191.97  4871.5 1184.13  4908.9 1176.84
  4916.0 1174.68  4931.4 1173.59  4936.6 1172.61  4966.1 1172.11  4976.3 1170.97
  4999.4 1165.85  4999.9 1165.35  5017.9 1165.35  5018.4 1165.85  5022.7 1168.55
  5029.0 1169.48  5049.2 1169.81  5099.5 1173.73  5110.3 1175.28  5137.8 1176.24
  5160.0 1176.90  5187.8 1178.97  5220.4 1182.20  5270.3 1185.89  5290.9 1188.61
  5301.0 1188.89  5341.9 1192.22  5357.9 1193.69  5362.9 1192.84  5401.7 1193.98
#Mann=6,-1,0
  4774.2    0.05       0  4936.6    0.12       0  4999.4    0.07       0
  5018.4    0.12       0  5137.8    0.05       0  5341.9    0.12       0
Bank Sta=4999.4,5018.4
Exp/Cntr=0.3,0.1

Type RM Length L Ch R = 1,13000,500,500,500
BEGIN DESCRIPTION:
BENNETT CREEK 26.0
END DESCRIPTION:
XS GIS Cut Line= 3
      2772406.15     10214856.86      2772751.88     10214838.86
      2772943.74     10214667.72
#Sta/Elev= 30
  4653.8 1182.31  4713.4 1182.28  4763.5 1180.81  4783.5 1178.29  4793.5 1177.81
  4843.6 1173.43  4873.6 1170.36  4923.7 1169.21  4938.6 1168.22  4953.7 1166.36
  4983.8 1165.86  4989.9 1164.86  4990.4 1164.36  5008.4 1164.36  5008.9 1164.86
  5014.0 1168.50  5028.2 1170.87  5043.5 1171.94  5052.4 1172.49  5070.8 1173.72
  5077.5 1175.14  5098.9 1178.06  5120.2 1180.34  5126.9 1180.55  5134.4 1181.83
  5148.6 1183.07  5190.1 1185.36  5219.5 1187.13  5240.5 1187.73  5257.1 1189.11
#Mann=7,-1,0
  4653.8    0.05       0  4938.6    0.12       0  4989.9    0.07       0
  5008.9    0.12       0  5043.5    0.05       0  5052.4    0.12       0
  5190.1    0.05       0
Bank Sta=4989.9,5008.9
Exp/Cntr=0.3,0.1

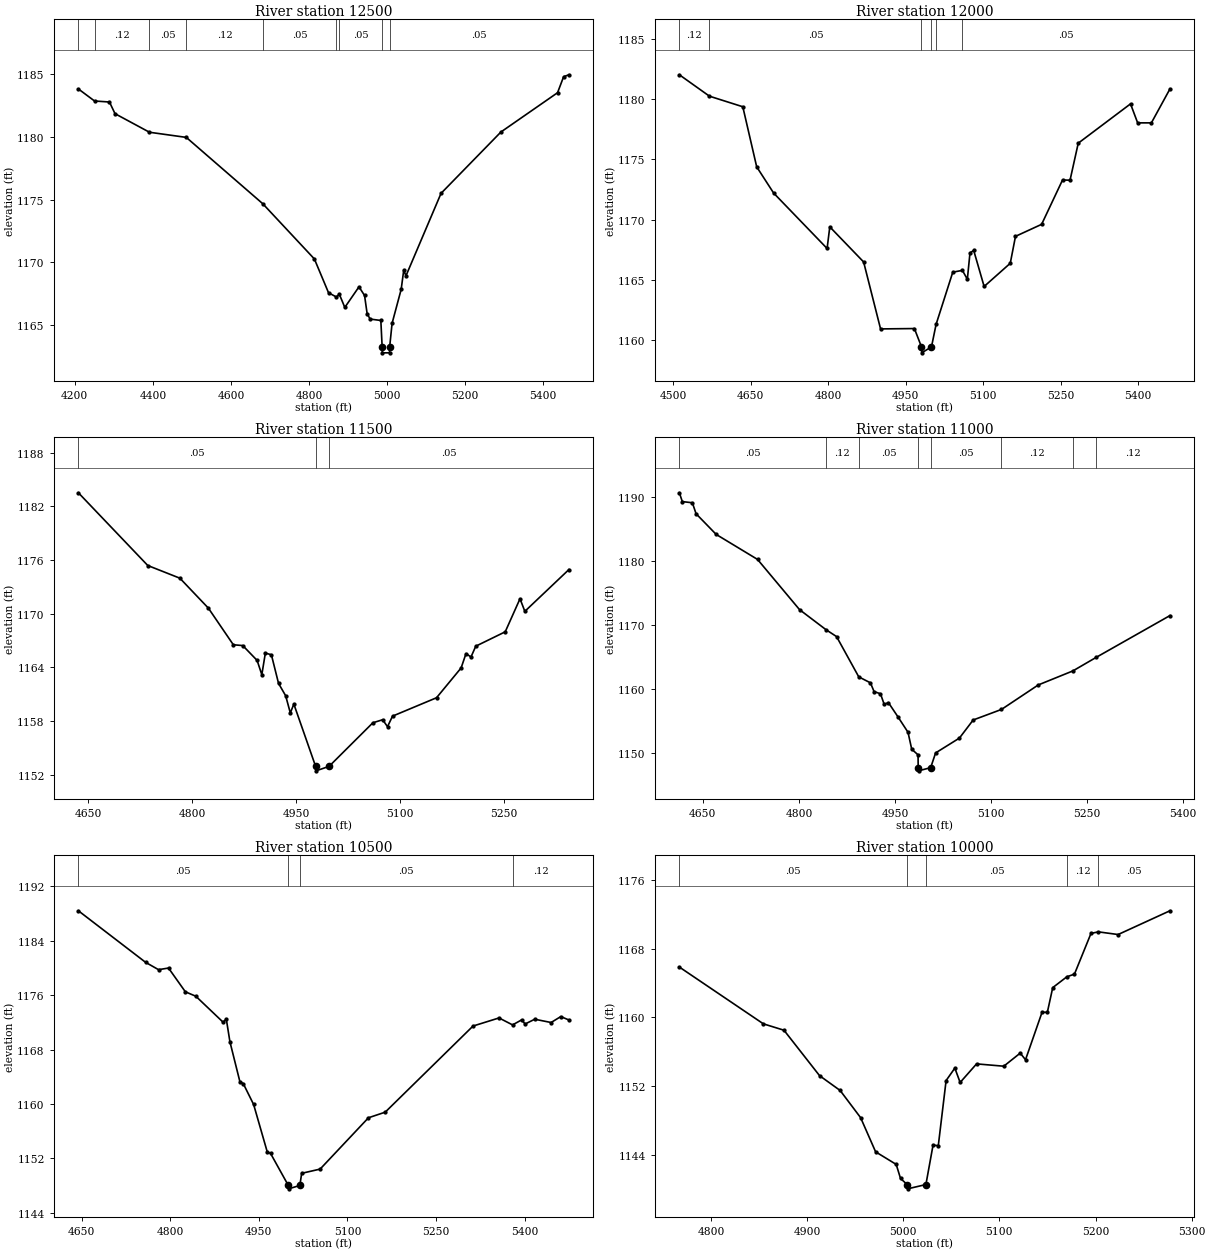
Type RM Length L Ch R = 1,12500,500,500,500
BEGIN DESCRIPTION:
BENNETT CREEK 25.0
END DESCRIPTION:
XS GIS Cut Line= 3
      2772216.55     10214789.58      2772818.74     10215302.14
      2773055.66     10215703.07
#Sta/Elev= 30
  4209.2 1183.81  4250.6 1182.85  4288.8 1182.77  4303.0 1181.84  4391.3 1180.36
  4485.6 1179.95  4681.6 1174.66  4813.7 1170.26  4849.9 1167.57  4870.0 1167.23
  4877.6 1167.45  4891.6 1166.40  4927.9 1168.04  4942.2 1167.35  4948.8 1165.90
  4956.5 1165.47  4983.9 1165.36  4987.2 1163.28  4987.7 1162.78  5006.1 1162.78
  5006.6 1163.28  5012.7 1165.13  5036.0 1167.84  5042.5 1169.36  5048.3 1168.92
  5138.1 1175.49  5291.5 1180.38  5436.5 1183.51  5452.1 1184.79  5465.7 1184.94
#Mann=9,-1,0
  4209.2    0.05       0  4250.6    0.12       0  4391.3    0.05       0
  4485.6    0.12       0  4681.6    0.05       0  4870.0    0.12       0
  4877.6    0.05       0  4987.2    0.05       0  5006.6    0.05       0
Bank Sta=4987.2,5006.6
Exp/Cntr=0.3,0.1

Type RM Length L Ch R = 1,12000,500,500,500
BEGIN DESCRIPTION:
BENNETT CREEK 24.0
END DESCRIPTION:
XS GIS Cut Line= 3
      2772216.56     10214905.74      2772359.54     10215372.33
      2772430.50     10215828.54
#Sta/Elev= 30
  4512.0 1182.04  4570.2 1180.26  4634.8 1179.38  4661.7 1174.38  4694.5 1172.20
  4798.0 1167.59  4803.2 1169.39  4868.7 1166.47  4901.5 1160.90  4967.0 1160.93
  4980.7 1159.41  4981.2 1158.91  5000.1 1159.41  5009.0 1161.28  5041.3 1165.62
  5059.9 1165.77  5069.5 1165.03  5074.6 1167.22  5081.8 1167.43  5102.0 1164.43
  5152.6 1166.36  5162.7 1168.60  5213.3 1169.60  5253.8 1173.29  5268.3 1173.27
  5284.2 1176.35  5385.4 1179.62  5399.2 1178.04  5425.8 1178.04  5461.7 1180.86
#Mann=6,-1,0
  4512.0    0.12       0  4570.2    0.05       0  4980.7    0.05       0
  5000.1    0.05       0  5009.0    0.12       0  5059.9    0.05       0
Bank Sta=4980.7,5000.1
Exp/Cntr=0.3,0.1

Type RM Length L Ch R = 1,11500,500,500,500
BEGIN DESCRIPTION:
BENNETT CREEK 23.0
END DESCRIPTION:
XS GIS Cut Line= 3
      2771955.67     10215003.15      2771866.80     10215356.24
      2772105.66     10215603.09
#Sta/Elev= 30
  4635.9 1183.53  4736.0 1175.39  4782.3 1173.97  4823.4 1170.62  4859.4 1166.52
  4873.0 1166.43  4893.7 1164.77  4900.5 1163.17  4905.6 1165.59  4914.3 1165.40
  4924.6 1162.20  4934.9 1160.81  4941.6 1158.89  4946.7 1159.88  4978.1 1152.91
  4978.6 1152.41  4997.5 1152.91  5060.7 1157.79  5074.8 1158.13  5081.8 1157.35
  5089.0 1158.53  5152.5 1160.59  5188.0 1163.93  5195.0 1165.53  5202.2 1165.15
  5209.1 1166.36  5251.6 1167.97  5272.9 1171.67  5279.9 1170.26  5343.5 1174.94
#Mann=3,-1,0
  4635.9    0.05       0  4978.1    0.05       0  4997.5    0.05       0
Bank Sta=4978.1,4997.5
Exp/Cntr=0.3,0.1

Type RM Length L Ch R = 1,11000,500,500,500
BEGIN DESCRIPTION:
BENNETT CREEK 22.0
END DESCRIPTION:
XS GIS Cut Line= 3
      2771043.41     10215217.76      2771377.72     10215412.13
      2771705.66     10215603.10
#Sta/Elev= 30
  4613.3 1190.72  4617.9 1189.34  4633.6 1189.16  4639.4 1187.44  4670.8 1184.21
  4735.4 1180.30  4801.0 1172.45  4842.4 1169.31  4858.8 1168.24  4893.5 1161.94
  4911.7 1161.01  4917.4 1159.64  4927.4 1159.30  4933.2 1157.64  4939.8 1157.92
  4954.7 1155.69  4970.4 1153.28  4976.2 1150.63  4986.1 1149.75  4986.3 1147.75
  4986.8 1147.25  5005.8 1147.75  5013.5 1150.05  5050.7 1152.37  5072.2 1155.20
  5116.4 1156.85  5173.9 1160.68  5227.9 1162.87  5264.5 1165.00  5379.5 1171.52
#Mann=8,-1,0
  4613.3    0.05       0  4842.4    0.12       0  4893.5    0.05       0
  4986.3    0.05       0  5005.8    0.05       0  5116.4    0.12       0
  5227.9    0.05       0  5264.5    0.12       0
Bank Sta=4986.3,5005.8
Exp/Cntr=0.3,0.1

Type RM Length L Ch R = 1,10500,500,500,500
BEGIN DESCRIPTION:
BENNETT CREEK 21.0
END DESCRIPTION:
XS GIS Cut Line= 3
      2771012.16     10215971.20      2771335.79     10215824.55
      2771755.68     10215603.12
#Sta/Elev= 30
  4644.7 1188.38  4758.4 1180.81  4780.3 1179.73  4797.2 1179.97  4825.7 1176.48
  4843.4 1175.83  4889.5 1172.02  4895.0 1172.46  4901.1 1169.14  4918.1 1163.23
  4923.6 1163.01  4941.2 1159.93  4964.3 1152.95  4969.8 1152.75  4999.9 1148.04
  5000.4 1147.54  5019.4 1148.04  5022.5 1149.82  5053.7 1150.44  5135.5 1157.98
  5163.8 1158.80  5312.4 1171.45  5356.4 1172.64  5379.3 1171.62  5394.8 1172.36
  5400.5 1171.75  5416.8 1172.45  5444.5 1171.97  5460.9 1172.84  5474.7 1172.34
#Mann=4,-1,0
  4644.7    0.05       0  4999.9    0.05       0  5019.4    0.05       0
  5379.3    0.12       0
Bank Sta=4999.9,5019.4
Exp/Cntr=0.3,0.1

Type RM Length L Ch R = 1,10000,500,500,500
BEGIN DESCRIPTION:
BENNETT CREEK 20.0
END DESCRIPTION:
XS GIS Cut Line= 3
      2771455.73     10216303.09      2771655.43     10216183.44
      2771905.69     10216303.11
#Sta/Elev= 30
  4767.2 1165.85  4854.6 1159.25  4876.0 1158.51  4913.0 1153.23  4934.4 1151.51
  4955.7 1148.35  4971.3 1144.38  4992.7 1142.92  4997.2 1141.29  5004.1 1140.58
  5004.6 1140.08  5023.6 1140.58  5031.0 1145.14  5036.5 1145.11  5044.6 1152.66
  5053.7 1154.11  5059.2 1152.44  5076.3 1154.60  5104.6 1154.33  5121.7 1155.85
  5127.2 1155.08  5144.4 1160.60  5149.9 1160.59  5155.5 1163.46  5170.2 1164.72
  5178.1 1165.03  5195.3 1169.76  5203.0 1169.94  5223.5 1169.63  5277.4 1172.39
#Mann=5,-1,0
  4767.2    0.05       0  5004.1    0.05       0  5023.6    0.05       0
  5170.2    0.12       0  5203.0    0.05       0
Bank Sta=5004.1,5023.6
Exp/Cntr=0.3,0.1