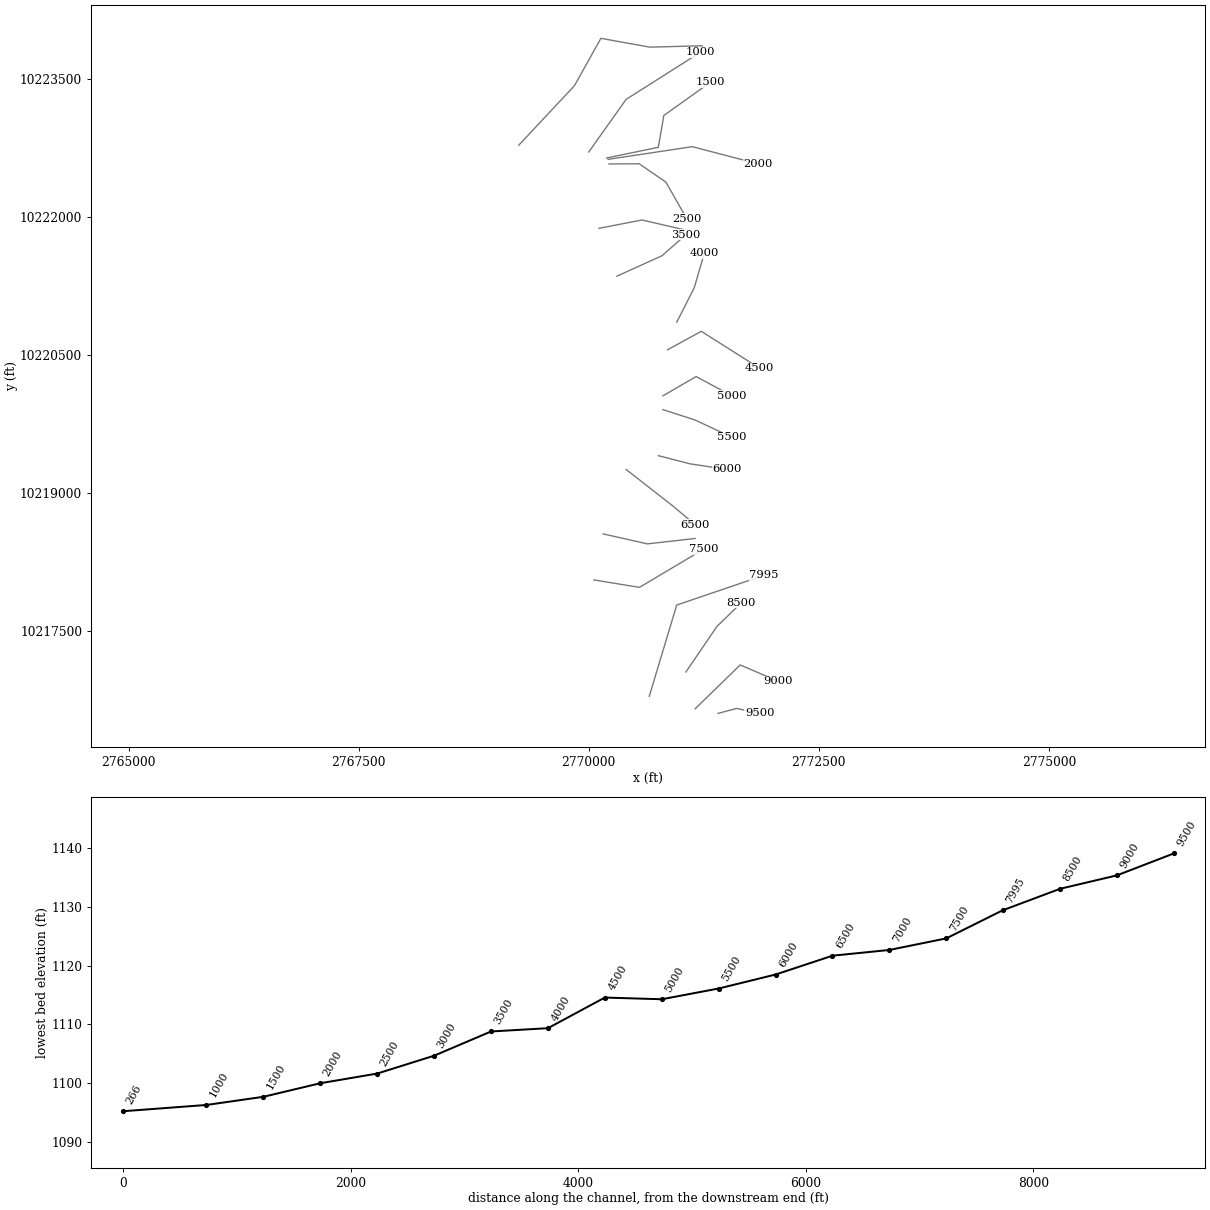
HEC-RAS study BENNETT CREEK.prj: BENNETT CREEK Base Level Engineering

--- BENNETT CREEK.g01 (geometry) --- (continued)

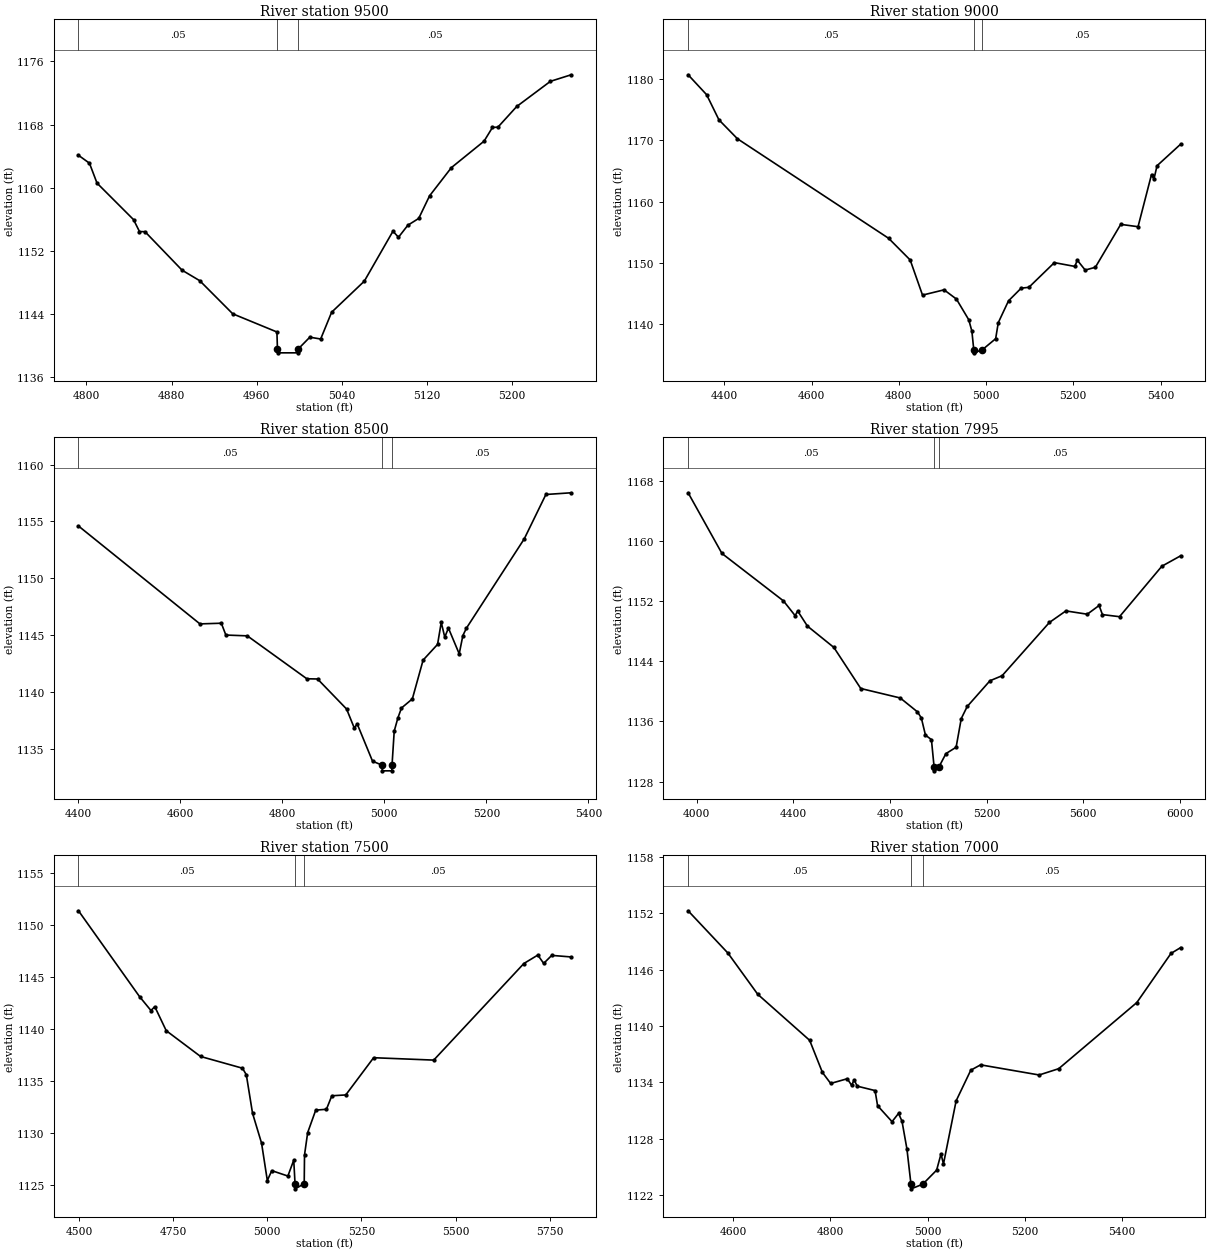
Type RM Length L Ch R = 1,9500,500,500,500
BEGIN DESCRIPTION:
BENNETT CREEK 19.0
END DESCRIPTION:
XS GIS Cut Line= 3
      2771405.72     10216603.12      2771606.00     10216656.98
      2771855.66     10216603.12
#Sta/Elev= 30
  4792.6 1164.12  4802.9 1163.12  4810.0 1160.60  4844.3 1155.98  4849.9 1154.47
  4855.1 1154.45  4889.9 1149.58  4906.5 1148.25  4937.5 1144.06  4979.0 1141.76
  4979.5 1139.62  4980.0 1139.12  4998.6 1139.12  4999.1 1139.62  5009.9 1141.10
  5020.1 1140.87  5030.4 1144.26  5061.1 1148.19  5088.0 1154.51  5093.2 1153.75
  5102.0 1155.27  5112.2 1156.13  5122.4 1158.99  5142.9 1162.56  5173.6 1165.91
  5181.5 1167.65  5186.6 1167.68  5204.3 1170.30  5235.9 1173.48  5255.4 1174.31
#Mann=3,-1,0
  4792.6    0.05       0  4979.5    0.05       0  4999.1    0.05       0
Bank Sta=4979.5,4999.1
Exp/Cntr=0.3,0.1

Type RM Length L Ch R = 1,9000,500,500,500
BEGIN DESCRIPTION:
BENNETT CREEK 18.0
END DESCRIPTION:
XS GIS Cut Line= 3
      2771155.65     10216653.08      2771645.47     10217129.36
      2772055.70     10216953.10
#Sta/Elev= 30
  4316.8 1180.66  4359.2 1177.42  4387.5 1173.32  4429.9 1170.24  4776.6 1154.03
  4826.0 1150.50  4854.3 1144.78  4903.7 1145.64  4932.0 1144.14  4960.3 1140.77
  4967.5 1138.91  4971.8 1135.88  4972.3 1135.38  4991.4 1135.88  5022.0 1137.68
  5028.0 1140.29  5051.5 1143.85  5080.5 1145.91  5098.2 1146.05  5156.6 1150.07
  5203.7 1149.45  5209.1 1150.48  5227.3 1148.86  5250.6 1149.31  5308.8 1156.30
  5348.5 1155.92  5379.4 1164.42  5384.9 1163.66  5392.1 1165.85  5446.5 1169.38
#Mann=3,-1,0
  4316.8    0.05       0  4971.8    0.05       0  4991.4    0.05       0
Bank Sta=4971.8,4991.4
Exp/Cntr=0.3,0.1

Type RM Length L Ch R = 1,8500,505,505,505
BEGIN DESCRIPTION:
BENNETT CREEK 17.0
END DESCRIPTION:
XS GIS Cut Line= 3
      2771055.69     10217053.12      2771392.86     10217548.09
      2771655.68     10217803.10
#Sta/Elev= 30
  4401.1 1154.60  4639.0 1146.00  4680.9 1146.06  4689.8 1145.02  4731.8 1144.95
  4848.4 1141.18  4869.4 1141.16  4926.3 1138.52  4941.2 1136.87  4947.2 1137.20
  4977.1 1133.94  4995.7 1133.59  4996.2 1133.09  5014.8 1133.09  5015.3 1133.59
  5019.6 1136.58  5026.8 1137.74  5033.8 1138.61  5055.1 1139.41  5076.2 1142.82
  5104.5 1144.20  5111.7 1146.13  5118.6 1144.84  5125.8 1145.63  5146.9 1143.37
  5154.1 1144.98  5161.1 1145.63  5274.3 1153.47  5316.7 1157.37  5366.2 1157.52
#Mann=3,-1,0
  4401.1    0.05       0  4995.7    0.03       0  5015.3    0.05       0
Bank Sta=4995.7,5015.3
Exp/Cntr=0.3,0.1

Type RM Length L Ch R = 1,7995,495,495,495
BEGIN DESCRIPTION:
BENNETT CREEK 16.0
END DESCRIPTION:
XS GIS Cut Line= 3
      2770657.39     10216789.07      2770955.50     10217780.00
      2771905.67     10218103.11
#Sta/Elev= 30
  3965.2 1166.40  4105.2 1158.33  4359.7 1152.02  4408.0 1150.06  4418.5 1150.68
  4458.8 1148.67  4568.3 1145.83  4679.5 1140.37  4842.9 1139.11  4914.2 1137.26
  4930.2 1136.45  4947.2 1134.17  4971.9 1133.57  4983.0 1129.92  4983.5 1129.42
  5002.7 1129.92  5031.9 1131.71  5074.1 1132.56  5095.3 1136.37  5120.0 1137.98
  5214.1 1141.40  5264.3 1142.07  5459.9 1149.15  5528.3 1150.69  5616.7 1150.25
  5665.6 1151.41  5679.5 1150.20  5750.1 1149.92  5925.2 1156.63  6003.6 1158.03
#Mann=3,-1,0
  3965.2    0.05       0  4983.0    0.05       0  5002.7    0.05       0
Bank Sta=4983,5002.7
Exp/Cntr=0.3,0.1

Type RM Length L Ch R = 1,7500,500,500,500
BEGIN DESCRIPTION:
BENNETT CREEK 15.0
END DESCRIPTION:
XS GIS Cut Line= 3
      2770055.67     10218053.11      2770550.77     10217971.97
      2771244.35     10218384.91
#Sta/Elev= 30
  4498.3 1151.38  4660.4 1143.13  4690.8 1141.79  4701.0 1142.16  4731.4 1139.85
  4822.6 1137.37  4934.0 1136.24  4944.2 1135.61  4960.7 1131.91  4984.7 1129.03
  5000.0 1125.44  5011.8 1126.39  5054.6 1125.87  5070.2 1127.40  5073.6 1125.14
  5074.1 1124.64  5098.0 1125.14  5098.8 1127.90  5107.2 1130.05  5128.6 1132.21
  5157.0 1132.29  5171.4 1133.59  5208.4 1133.67  5282.4 1137.25  5442.1 1137.02
  5681.6 1146.31  5718.6 1147.12  5734.2 1146.32  5755.6 1147.09  5807.2 1146.94
#Mann=3,-1,0
  4498.3    0.05       0  5073.6    0.05       0  5098.0    0.05       0
Bank Sta=5073.6,5098
Exp/Cntr=0.3,0.1

Type RM Length L Ch R = 1,7000,500,500,500
BEGIN DESCRIPTION:
BENNETT CREEK 14.0
END DESCRIPTION:
XS GIS Cut Line= 3
      2770155.71     10218553.11      2770637.01     10218444.54
      2771155.72     10218503.12
#Sta/Elev= 30
  4506.6 1152.27  4588.6 1147.77  4650.1 1143.38  4757.1 1138.48  4783.4 1135.06
  4800.4 1133.89  4834.6 1134.39  4843.6 1133.69  4848.7 1134.27  4855.1 1133.60
  4891.9 1133.13  4897.1 1131.52  4926.9 1129.82  4940.3 1130.70  4947.4 1129.87
  4957.6 1126.91  4965.9 1123.17  4966.4 1122.67  4990.3 1123.17  5018.8 1124.66
  5027.8 1126.38  5032.9 1125.32  5059.0 1132.04  5089.2 1135.30  5109.4 1135.87
  5230.1 1134.79  5270.4 1135.46  5431.4 1142.50  5501.8 1147.73  5522.0 1148.36
#Mann=3,-1,0
  4506.6    0.05       0  4965.9    0.03       0  4990.3    0.05       0
Bank Sta=4965.9,4990.3
Exp/Cntr=0.3,0.1

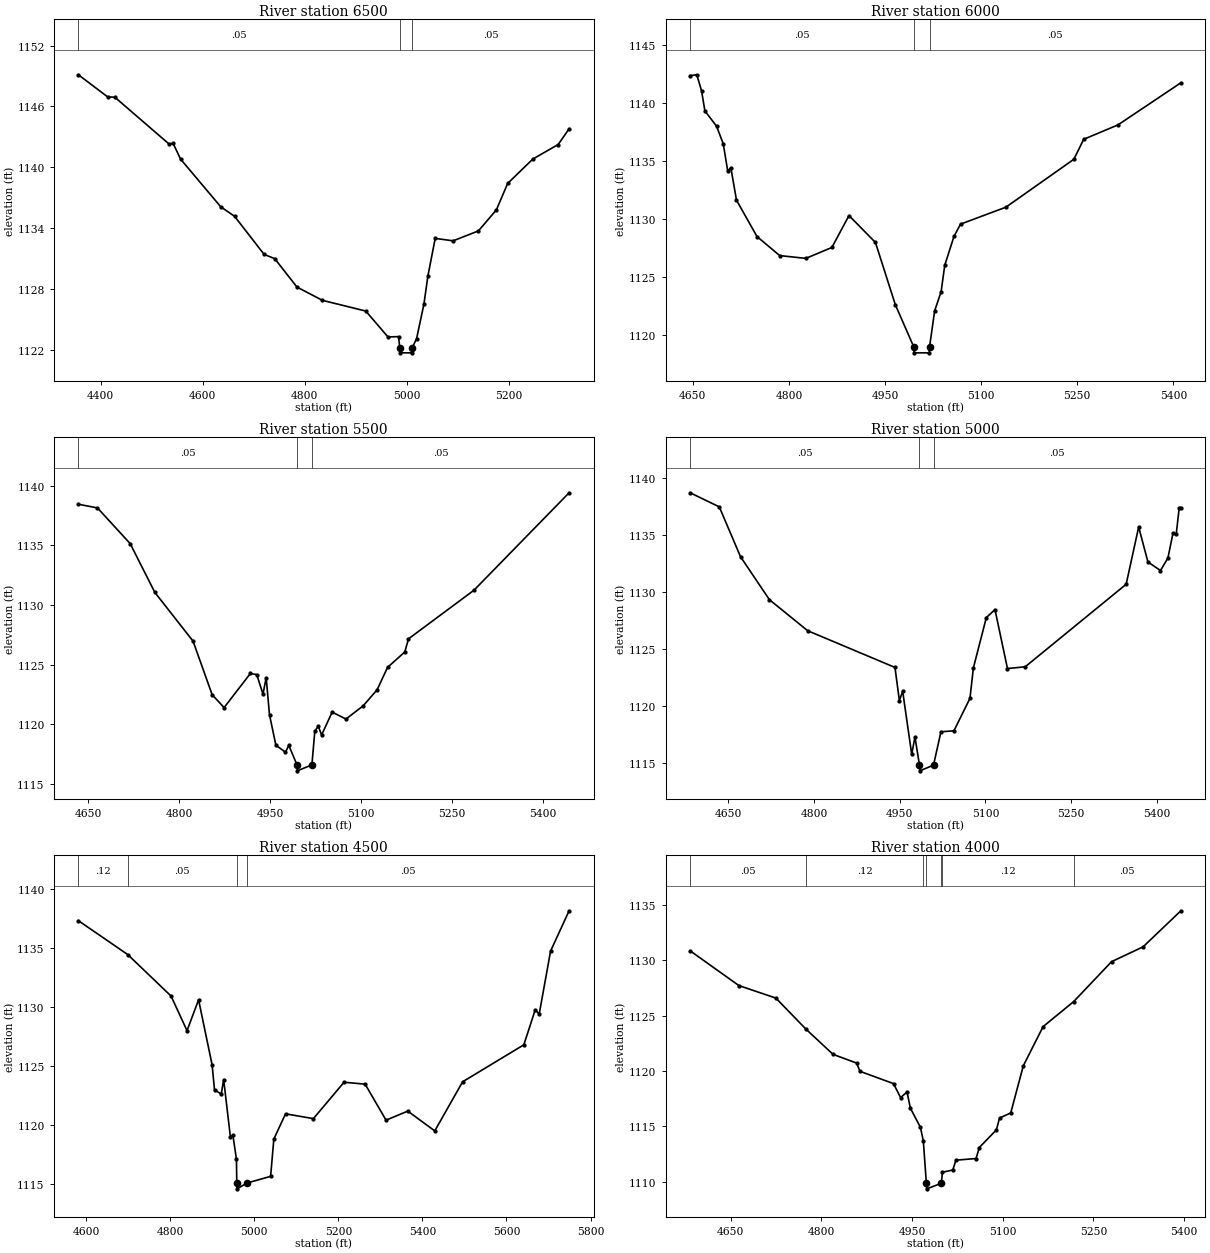
Type RM Length L Ch R = 1,6500,500,500,500
BEGIN DESCRIPTION:
BENNETT CREEK 13.0
END DESCRIPTION:
XS GIS Cut Line= 3
      2770405.66     10219253.13      2770912.61     10218857.12
      2771155.66     10218653.13
#Sta/Elev= 30
  4356.7 1149.12  4413.7 1146.95  4428.2 1146.90  4534.4 1142.28  4542.1 1142.36
  4556.6 1140.81  4635.3 1136.10  4662.4 1135.16  4720.3 1131.40  4741.1 1130.98
  4784.5 1128.18  4834.3 1126.87  4919.3 1125.81  4962.7 1123.26  4983.5 1123.29
  4985.7 1122.19  4986.2 1121.69  5009.7 1121.69  5010.2 1122.19  5018.8 1123.10
  5033.1 1126.50  5040.9 1129.28  5055.2 1132.98  5090.3 1132.74  5139.8 1133.72
  5174.9 1135.79  5197.0 1138.40  5246.4 1140.81  5295.9 1142.24  5317.3 1143.79
#Mann=3,-1,0
  4356.7    0.05       0  4985.7    0.03       0  5010.2    0.05       0
Bank Sta=4985.7,5010.2
Exp/Cntr=0.3,0.1

Type RM Length L Ch R = 1,6000,500,500,500
BEGIN DESCRIPTION:
BENNETT CREEK 12.0
END DESCRIPTION:
XS GIS Cut Line= 3
      2770755.65     10219403.12      2771098.63     10219314.67
      2771505.70     10219253.11
#Sta/Elev= 30
  4645.8 1142.37  4656.2 1142.44  4663.6 1141.05  4668.8 1139.33  4687.1 1138.00
  4697.5 1136.48  4704.3 1134.19  4709.4 1134.40  4718.1 1131.64  4750.1 1128.50
  4785.6 1126.86  4826.3 1126.62  4867.0 1127.56  4893.7 1130.31  4935.0 1127.99
  4966.0 1122.63  4994.9 1118.98  4995.4 1118.48  5018.9 1118.48  5019.4 1118.98
  5027.4 1122.10  5037.5 1123.75  5043.2 1126.04  5057.7 1128.53  5067.8 1129.57
  5138.6 1131.03  5244.7 1135.16  5260.0 1136.88  5313.5 1138.12  5411.7 1141.75
#Mann=3,-1,0
  4645.8    0.05       0  4994.9    0.05       0  5019.4    0.05       0
Bank Sta=4994.9,5019.4
Exp/Cntr=0.3,0.1

Type RM Length L Ch R = 1,5500,500,500,500
BEGIN DESCRIPTION:
BENNETT CREEK 11.0
END DESCRIPTION:
XS GIS Cut Line= 3
      2770805.70     10219903.11      2771153.93     10219790.78
      2771555.66     10219603.12
#Sta/Elev= 30
  4634.1 1138.44  4665.6 1138.13  4719.5 1135.14  4760.2 1131.05  4823.2 1126.97
  4854.7 1122.48  4874.4 1121.40  4917.8 1124.26  4928.3 1124.16  4938.5 1122.53
  4943.8 1123.90  4949.3 1120.79  4959.8 1118.25  4975.6 1117.66  4981.1 1118.24
  4994.6 1116.60  4995.1 1116.10  5019.2 1116.60  5024.0 1119.42  5029.7 1119.85
  5035.2 1119.10  5052.6 1121.02  5075.4 1120.44  5103.8 1121.55  5126.7 1122.89
  5144.0 1124.77  5172.4 1126.06  5178.5 1127.16  5286.6 1131.24  5443.4 1139.40
#Mann=3,-1,0
  4634.1    0.05       0  4994.6    0.05       0  5019.2    0.05       0
Bank Sta=4994.6,5019.2
Exp/Cntr=0.3,0.1

Type RM Length L Ch R = 1,5000,500,500,500
BEGIN DESCRIPTION:
BENNETT CREEK 10.0
END DESCRIPTION:
XS GIS Cut Line= 3
      2770805.64     10220053.09      2771166.13     10220262.51
      2771555.71     10220053.10
#Sta/Elev= 30
  4583.1 1138.74  4634.1 1137.50  4671.3 1133.11  4721.9 1129.33  4788.9 1126.60
  4941.7 1123.37  4949.4 1120.46  4955.2 1121.27  4971.0 1115.72  4976.7 1117.25
  4984.6 1114.77  4985.1 1114.27  5009.2 1114.77  5022.2 1117.71  5044.9 1117.79
  5073.0 1120.65  5079.0 1123.33  5101.7 1127.76  5116.8 1128.46  5138.7 1123.27
  5169.8 1123.43  5346.5 1130.69  5368.4 1135.73  5384.6 1132.65  5406.6 1131.90
  5419.6 1133.00  5428.5 1135.19  5434.1 1135.07  5439.4 1137.43  5442.3 1137.43
#Mann=3,-1,0
  4583.1    0.05       0  4984.6    0.05       0  5009.2    0.05       0
Bank Sta=4984.6,5009.2
Exp/Cntr=0.3,0.1

Type RM Length L Ch R = 1,4500,500,500,500
BEGIN DESCRIPTION:
BENNETT CREEK 9.0
END DESCRIPTION:
XS GIS Cut Line= 3
      2770855.69     10220553.11      2771222.93     10220754.01
      2771855.72     10220353.09
#Sta/Elev= 30
  4581.4 1137.33  4698.9 1134.45  4801.9 1130.93  4839.9 1127.99  4867.4 1130.61
  4899.6 1125.09  4905.3 1122.96  4921.4 1122.61  4927.1 1123.84  4943.2 1118.94
  4948.9 1119.15  4957.5 1117.07  4958.3 1115.06  4958.8 1114.56  4983.2 1115.06
  5038.8 1115.62  5046.5 1118.79  5074.3 1120.93  5140.6 1120.52  5213.5 1123.61
  5263.7 1123.45  5313.5 1120.39  5365.2 1121.16  5429.4 1119.48  5495.7 1123.65
  5641.4 1126.79  5668.5 1129.77  5677.9 1129.39  5705.0 1134.75  5749.1 1138.17
#Mann=4,-1,0
  4581.4    0.12       0  4698.9    0.05       0  4958.3    0.05       0
  4983.2    0.05       0
Bank Sta=4958.3,4983.2
Exp/Cntr=0.3,0.1

Type RM Length L Ch R = 1,4000,500,500,500
BEGIN DESCRIPTION:
BENNETT CREEK 8.0
END DESCRIPTION:
XS GIS Cut Line= 3
      2770955.68     10220853.11      2771144.89     10221224.38
      2771255.68     10221603.11
#Sta/Elev= 30
  4583.3 1130.85  4663.9 1127.71  4725.0 1126.58  4774.8 1123.77  4819.6 1121.49
  4858.4 1120.71  4864.1 1119.96  4919.5 1118.85  4931.2 1117.59  4941.8 1118.09
  4947.4 1116.63  4964.0 1114.90  4968.8 1113.67  4973.8 1109.84  4974.3 1109.34
  4998.7 1109.84  5000.3 1110.84  5017.5 1111.04  5022.7 1111.93  5056.0 1112.08
  5061.3 1113.07  5089.6 1114.67  5094.8 1115.74  5113.3 1116.20  5134.1 1120.46
  5166.8 1124.00  5217.3 1126.26  5280.0 1129.87  5332.1 1131.21  5394.6 1134.47
#Mann=7,-1,0
  4583.3    0.05       0  4774.8    0.12       0  4968.8    0.05       0
  4973.8    0.05       0  4998.7    0.05       0  5000.3    0.12       0
  5217.3    0.05       0
Bank Sta=4973.8,4998.7
Exp/Cntr=0.3,0.1

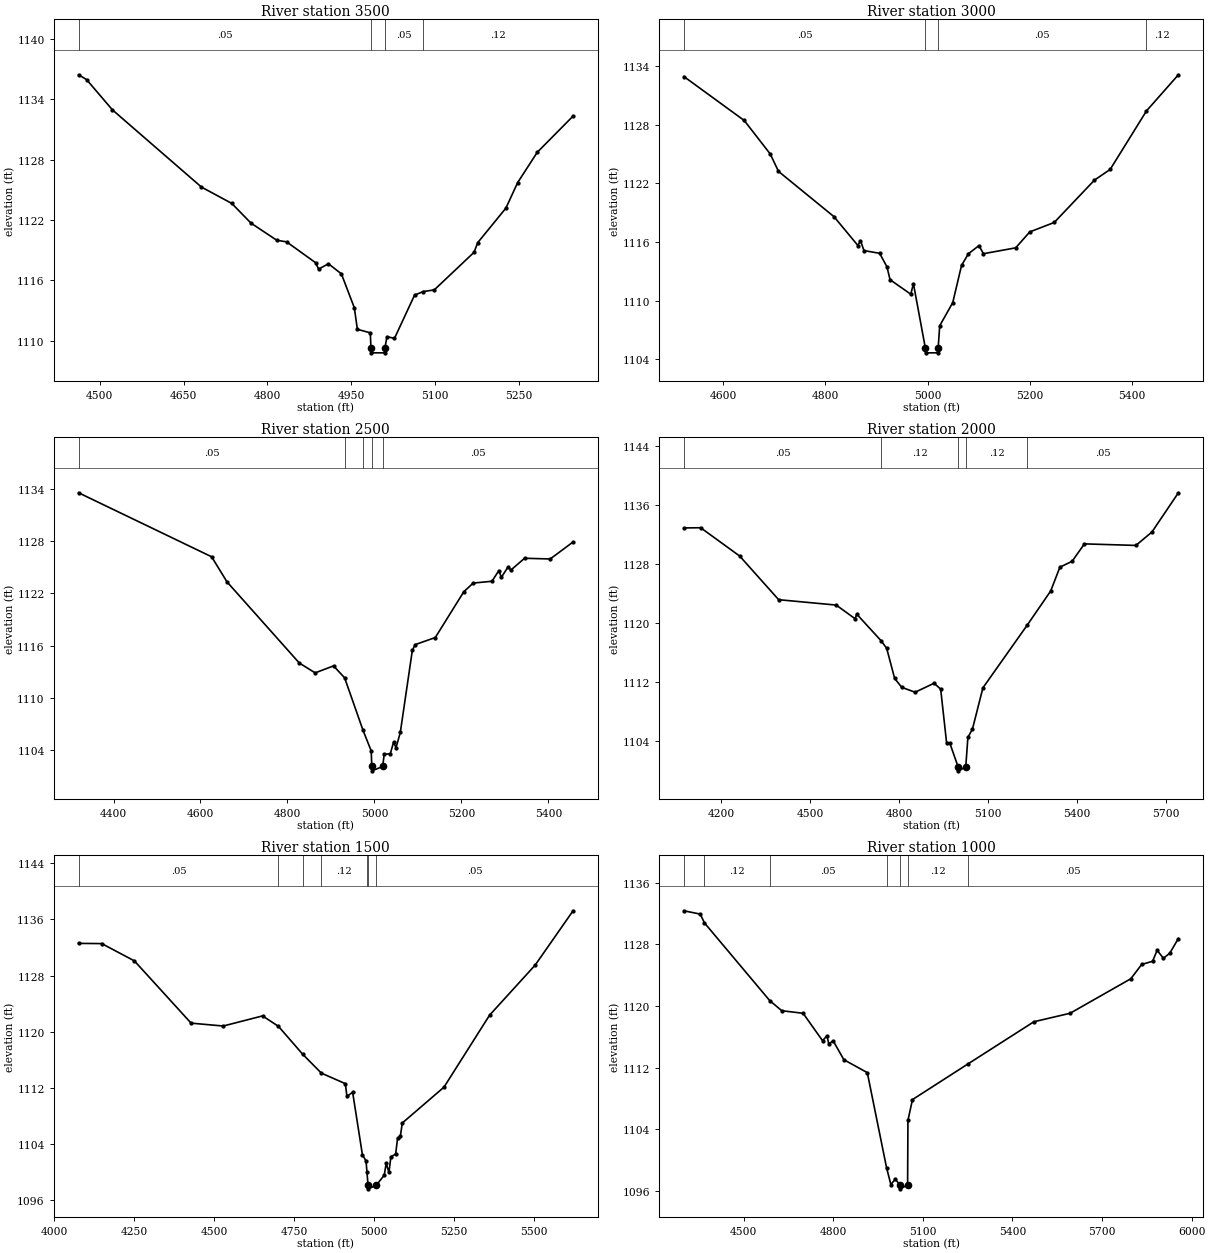
Type RM Length L Ch R = 1,3500,500,500,500
BEGIN DESCRIPTION:
BENNETT CREEK 7.0
END DESCRIPTION:
XS GIS Cut Line= 3
      2770305.64     10221353.09      2770795.39     10221574.80
      2771055.66     10221803.09
#Sta/Elev= 30
  4462.4 1136.44  4476.7 1135.96  4522.9 1132.95  4682.0 1125.27  4736.3 1123.64
  4770.4 1121.69  4816.6 1119.98  4834.2 1119.82  4885.9 1117.75  4891.4 1117.11
  4909.0 1117.64  4932.1 1116.64  4955.2 1113.27  4960.7 1111.12  4983.8 1110.77
  4984.9 1109.28  4985.4 1108.78  5009.5 1108.78  5010.0 1109.28  5013.6 1110.39
  5027.0 1110.22  5063.0 1114.53  5078.8 1114.88  5098.1 1115.04  5169.2 1118.78
  5175.9 1119.75  5226.2 1123.18  5247.1 1125.71  5282.2 1128.73  5346.2 1132.33
#Mann=4,-1,0
  4462.4    0.05       0  4984.9    0.03       0  5010.0    0.05       0
  5078.8    0.12       0
Bank Sta=4984.9,5010
Exp/Cntr=0.3,0.1

Type RM Length L Ch R = 1,3000,500,500,500
BEGIN DESCRIPTION:
BENNETT CREEK 6.0
END DESCRIPTION:
XS GIS Cut Line= 3
      2770109.87     10221872.81      2770577.98     10221963.43
      2771055.71     10221853.11
#Sta/Elev= 30
  4523.2 1132.94  4641.2 1128.44  4692.1 1125.01  4708.2 1123.23  4816.8 1118.59
  4863.5 1115.64  4868.6 1116.14  4875.4 1115.12  4906.0 1114.84  4920.3 1113.46
  4926.4 1112.14  4967.0 1110.65  4972.1 1111.74  4995.4 1105.15  4995.9 1104.65
  5020.0 1104.65  5020.5 1105.15  5023.5 1107.42  5049.0 1109.79  5066.2 1113.60
  5079.7 1114.80  5100.3 1115.63  5109.0 1114.80  5172.1 1115.40  5199.6 1117.03
  5247.5 1118.00  5326.1 1122.33  5356.9 1123.43  5427.9 1129.42  5490.3 1133.12
#Mann=4,-1,0
  4523.2    0.05       0  4995.4    0.05       0  5020.5    0.05       0
  5427.9    0.12       0
Bank Sta=4995.4,5020.5
Exp/Cntr=0.3,0.1

Type RM Length L Ch R = 1,2500,500,500,500
BEGIN DESCRIPTION:
BENNETT CREEK 5.0
END DESCRIPTION:
XS GIS Cut Line= 4
      2770219.80     10222572.26      2770547.51     10222574.37
      2770838.11     10222374.71      2771064.00     10221977.90
#Sta/Elev= 30
  4319.7 1133.54  4625.6 1126.19  4660.9 1123.31  4827.2 1113.99  4863.6 1112.86
  4905.9 1113.66  4931.4 1112.29  4973.7 1106.26  4992.5 1103.90  4993.8 1102.11
  4994.3 1101.61  5018.9 1102.11  5022.3 1103.50  5036.4 1103.58  5043.9 1104.89
  5049.6 1104.27  5059.4 1106.02  5087.1 1115.46  5093.9 1116.11  5139.9 1116.92
  5205.3 1122.17  5226.9 1123.17  5270.1 1123.38  5286.0 1124.61  5291.7 1123.83
  5307.6 1125.06  5313.3 1124.65  5345.1 1126.02  5404.1 1125.94  5456.6 1127.89
#Mann=5,-1,0
  4319.7    0.05       0  4931.4    0.12       0  4973.7    0.05       0
  4993.8    0.05       0  5018.9    0.05       0
Bank Sta=4993.8,5018.9
Exp/Cntr=0.3,0.1

Type RM Length L Ch R = 1,2000,500,500,500
BEGIN DESCRIPTION:
BENNETT CREEK 4.0
END DESCRIPTION:
XS GIS Cut Line= 3
      2770209.79     10222622.23      2771125.19     10222759.94
      2771842.12     10222572.62
#Sta/Elev= 30
  4074.3 1132.90  4130.8 1132.93  4262.3 1129.09  4393.7 1123.17  4587.7 1122.44
  4651.6 1120.58  4656.7 1121.22  4738.9 1117.61  4757.8 1116.58  4784.6 1112.50
  4808.4 1111.29  4853.6 1110.62  4917.5 1111.84  4939.8 1111.04  4960.0 1103.67
  4970.2 1103.76  4998.9 1100.46  4999.4 1099.96  5024.3 1100.46  5031.5 1104.49
  5046.9 1105.62  5082.2 1111.22  5231.8 1119.74  5310.6 1124.35  5341.6 1127.58
  5382.9 1128.38  5424.3 1130.74  5597.7 1130.53  5651.7 1132.34  5741.0 1137.67
#Mann=5,-1,0
  4074.3    0.05       0  4738.9    0.12       0  4998.9    0.07       0
  5024.3    0.12       0  5231.8    0.05       0
Bank Sta=4998.9,5024.3
Exp/Cntr=0.3,0.1

Type RM Length L Ch R = 1,1500,500,500,500
BEGIN DESCRIPTION:
BENNETT CREEK 3.0
END DESCRIPTION:
XS GIS Cut Line= 4
      2770194.77     10222637.21      2770755.68     10222753.11
      2770815.53     10223098.70      2771322.28     10223460.42
#Sta/Elev= 30
  4076.5 1132.58  4148.9 1132.55  4251.0 1130.09  4428.3 1121.23  4528.8 1120.82
  4651.8 1122.26  4701.5 1120.77  4777.3 1116.80  4835.5 1114.12  4910.5 1112.62
  4915.6 1110.81  4933.4 1111.39  4963.9 1102.51  4975.3 1101.61  4978.2 1100.02
  4981.6 1098.15  4982.1 1097.65  5007.1 1098.15  5032.2 1099.59  5038.3 1101.27
  5046.9 1099.99  5053.0 1102.21  5067.8 1102.60  5073.9 1104.83  5082.5 1105.13
  5088.7 1107.02  5219.0 1112.12  5361.5 1122.36  5504.1 1129.49  5622.6 1137.22
#Mann=7,-1,0
  4076.5    0.05       0  4701.5    0.12       0  4777.3    0.05       0
  4835.5    0.12       0  4978.2    0.05       0  4981.6    0.05       0
  5007.1    0.05       0
Bank Sta=4981.6,5007.1
Exp/Cntr=0.3,0.1

Type RM Length L Ch R = 1,1000,734,734,734
BEGIN DESCRIPTION:
BENNETT CREEK 2.0
END DESCRIPTION:
XS GIS Cut Line= 3
      2769999.92     10222702.16      2770405.35     10223273.53
      2771212.36     10223785.29
#Sta/Elev= 30
  4299.4 1132.37  4354.2 1131.94  4368.2 1130.80  4587.0 1120.70  4627.3 1119.39
  4698.6 1119.06  4763.8 1115.50  4778.6 1116.13  4784.7 1115.09  4799.5 1115.47
  4835.2 1113.03  4913.7 1111.35  4978.1 1099.02  4992.6 1096.82  5007.4 1097.52
  5023.2 1096.76  5023.7 1096.26  5048.7 1096.76  5049.8 1105.15  5065.0 1107.85
  5250.0 1112.46  5471.7 1117.96  5592.9 1119.06  5796.2 1123.54  5832.7 1125.40
  5869.1 1125.81  5884.4 1127.24  5905.5 1126.20  5926.7 1126.86  5955.6 1128.77
#Mann=7,-1,0
  4299.4    0.05       0  4368.2    0.12       0  4587.0    0.05       0
  4978.1    0.12       0  5023.2    0.07       0  5048.7    0.12       0
  5250.0    0.05       0
Bank Sta=5023.2,5048.7
Exp/Cntr=0.3,0.1

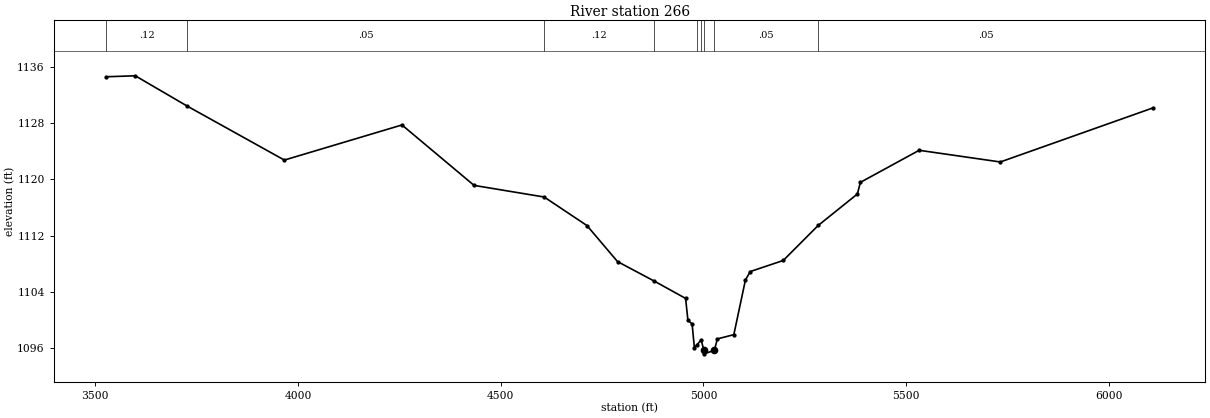
Type RM Length L Ch R = 1,266,0,0,0
BEGIN DESCRIPTION:
BENNETT CREEK 1.0
END DESCRIPTION:
XS GIS Cut Line= 5
      2769240.50     10222777.10      2769844.20     10223422.07
      2770131.75     10223937.00      2770664.41     10223841.28
      2771232.32     10223856.22
#Sta/Elev= 30
  3526.8 1134.57  3598.5 1134.71  3726.4 1130.41  3966.3 1122.73  4256.4 1127.72
  4434.3 1119.13  4607.2 1117.48  4712.8 1113.42  4788.2 1108.30  4879.1 1105.52
  4956.1 1103.07  4961.9 1099.93  4972.1 1099.46  4977.8 1096.05  4983.1 1096.39
  4994.4 1097.16  5001.3 1095.69  5001.8 1095.19  5027.0 1095.69  5034.5 1097.31
  5075.1 1097.92  5103.7 1105.69  5115.8 1106.89  5197.0 1108.46  5283.3 1113.44
  5379.9 1117.91  5387.2 1119.56  5532.3 1124.12  5732.5 1122.46  6109.3 1130.15
#Mann=9,-1,0
  3526.8    0.12       0  3726.4    0.05       0  4607.2    0.12       0
  4879.1    0.05       0  4983.1    0.12       0  4994.4    0.05       0
  5001.3    0.05       0  5027.0    0.05       0  5283.3    0.05       0
Bank Sta=5001.3,5027
Exp/Cntr=0.3,0.1

Chan Stop Cuts=-1