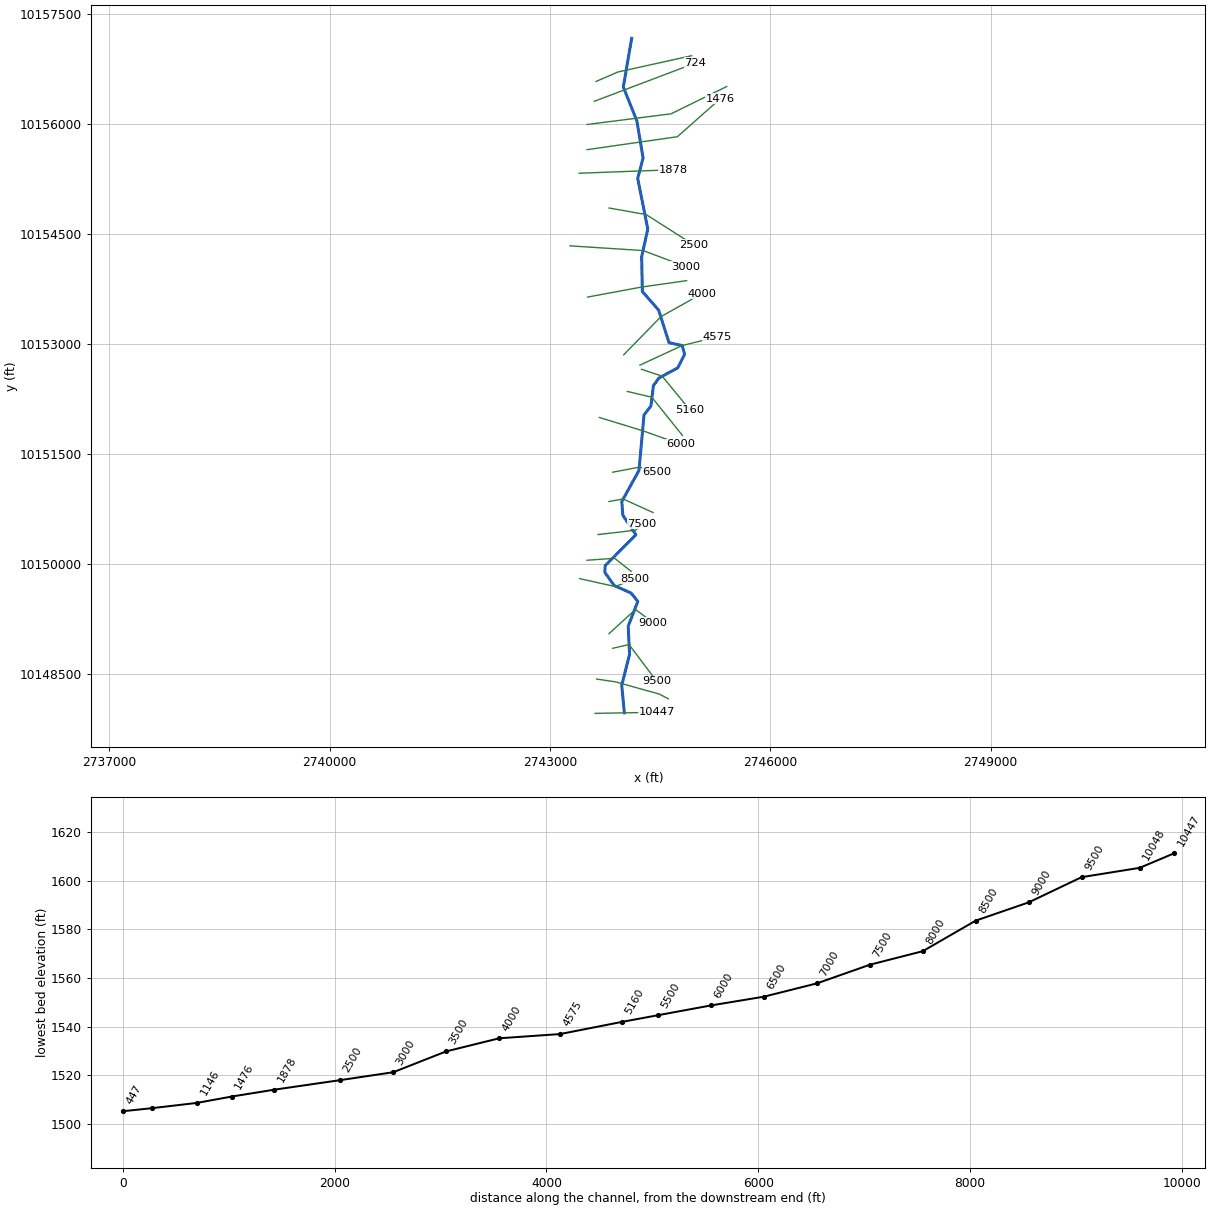
--- BERNST CREEK.prj (project) ---

Proj Title=BERNST CREEK Base Level Engineering
Current Plan=p01
Default Exp/Contr=0.3,0.1
English Units
Geom File=g01
Flow File=f01
Plan File=p01
Y Axis Title=Elevation
X Axis Title(PF)=Main Channel Distance
X Axis Title(XS)=Station
BEGIN DESCRIPTION:
BERNST CREEK
END DESCRIPTION:
DSS Export Rating Curves= 0
DSS Export Rating Curve Sorted= 0
DSS Export Volume Flow Curves= 0
DXF OffsetX= 0
DXF OffsetY= 0
DXF ScaleX= 1
DXF ScaleY= 10

--- BERNST CREEK.p01 (plan) ---

Plan Title=Multiple Run
Short Identifier=Multiple
Geom File=g01
Flow File=f01
Subcritical Flow
K Sum by GR= 0
Std Step Tol= 0.01
Critical Tol= 0.01
Num of Std Step Trials= 20
Max Error Tol= 0.3
Flow Tol Ratio= 0.001
Split Flow NTrial= 30
Split Flow Tol= 0.02
Split Flow Ratio= 0.02
Log Output Level= 0
Friction Slope Method= 1
Unsteady Friction Slope Method= 2
Unsteady Bridges Friction Slope Method= 1
Parabolic Critical Depth
Global Vel Dist=  1 , 1 , 1
Global Log Level= 0
CheckData=True
Encroach Param= -1, 0, 0, 0
BEGIN DESCRIPTION:
Multiple Run
END DESCRIPTION:

--- BERNST CREEK.f01 (steady flow) ---

Flow Title=Multiple
Program Version=4.10
Number of Profiles= 7
Profile Names=10-year,25-year,50-year,1pct_min,100-year,1pct_plu,500-year
River Rch & RM=BERNST CREEK,Reach-1         ,10447
    1485    2611    5316    3806    7736   15726   11089
River Rch & RM=BERNST CREEK,Reach-1         ,8500
    1784    3183    6477    4530    9492   19891   13622
River Rch & RM=BERNST CREEK,Reach-1         ,1878
    1879    3367    6761    4683    9914   20991   14215
Boundary for River Rch & Prof#=BERNST CREEK,Reach-1         , 1
Up Type= 0
Dn Type= 3
Dn Slope=0.005
Boundary for River Rch & Prof#=BERNST CREEK,Reach-1         , 2
Up Type= 0
Dn Type= 3
Dn Slope=0.005
Boundary for River Rch & Prof#=BERNST CREEK,Reach-1         , 3
Up Type= 0
Dn Type= 3
Dn Slope=0.005
Boundary for River Rch & Prof#=BERNST CREEK,Reach-1         , 4
Up Type= 0
Dn Type= 3
Dn Slope=0.005
Boundary for River Rch & Prof#=BERNST CREEK,Reach-1         , 5
Up Type= 0
Dn Type= 3
Dn Slope=0.005
Boundary for River Rch & Prof#=BERNST CREEK,Reach-1         , 6
Up Type= 0
Dn Type= 3
Dn Slope=0.005
Boundary for River Rch & Prof#=BERNST CREEK,Reach-1         , 7
Up Type= 0
Dn Type= 3
Dn Slope=0.005
DSS Import GetInterval= 0
DSS Import GetPeak= 0
DSS Import FillOption= 0

--- BERNST CREEK.g01 (geometry) ---

Geom Title=Existing Conditions
Program Version=4.10

River Reach=BERNST CREEK    ,Reach-1
Reach XY= 30
        2744014.       10147974.      2743978.75       10148349.
        2744085.       10148771.       2744066.5       10149155.
       2744197.5       10149493.        2744107.       10149605.
      2743873.75       10149710.      2743748.75       10149887.
      2743752.75       10149979.       2744171.5       10150400.
      2743993.75       10150666.      2743979.25       10150853.
      2744213.25       10151277.        2744282.       10152033.
      2744375.75       10152156.        2744410.       10152433.
        2744485.       10152537.       2744740.5       10152674.
        2744834.       10152859.      2744801.75       10152979.
       2744622.5       10153018.        2744481.       10153462.
        2744259.       10153715.      2744249.75       10154187.
        2744333.       10154566.        2744196.       10155257.
      2744269.25       10155534.        2744184.       10156042.
        2744000.       10156502.      2744113.75       10157165.

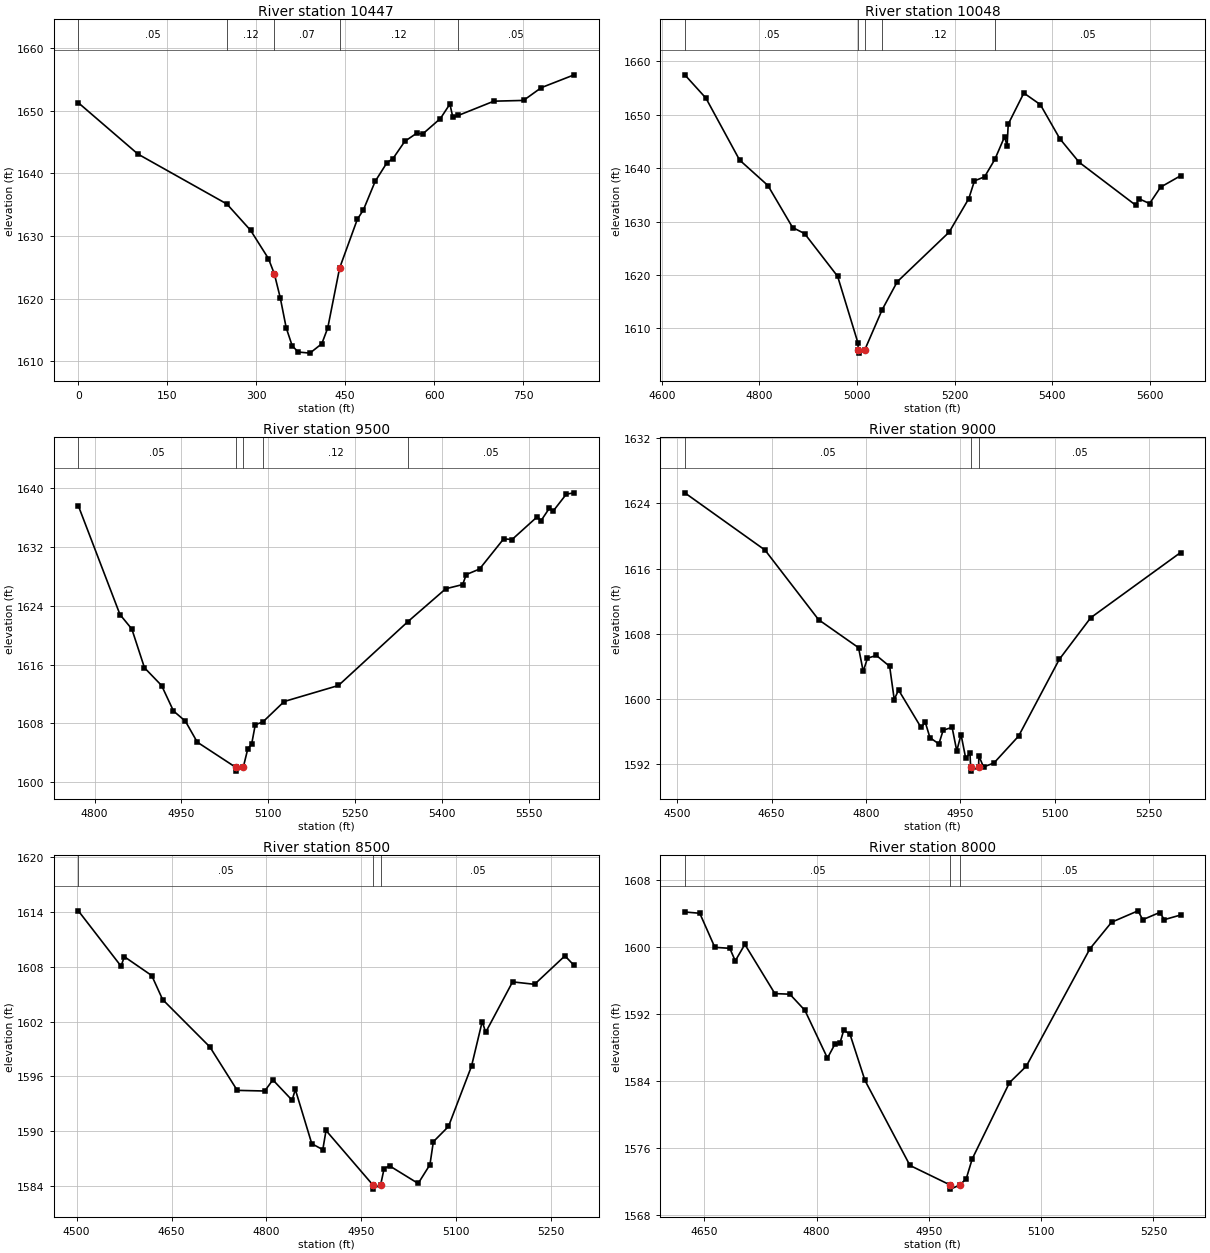
Type RM Length L Ch R = 1 ,10447   ,323,323,323
BEGIN DESCRIPTION:
BERNST CREEK 20.0
END DESCRIPTION:
XS GIS Cut Line= 3
      2743615.24     10147966.68        2744014.       10147974.
      2744451.54     10147981.87
#Sta/Elev= 30
       0 1651.28   100.5 1643.08   250.5  1635.1   290.5 1630.89   320.5 1626.39
   330.5 1623.94   340.5 1620.11   350.5 1615.32   360.5 1612.48   370.5 1611.46
   390.5 1611.28   410.5 1612.78   420.5 1615.29   440.5 1624.86   470.5 1632.68
   480.5 1634.13   500.5 1638.72   520.5 1641.72   530.5 1642.36   550.5 1645.12
   570.5 1646.41   580.5 1646.28   610.5 1648.76   626.5 1651.07   631.5 1648.93
   640.6 1649.25   700.6 1651.53   750.6 1651.65   780.6 1653.69     836 1655.74
#Mann= 5 ,-1 , 0
       0     .05       0   250.5     .12       0   330.5     .07       0
   440.5     .12       0   640.6     .05       0
Bank Sta=330.5,440.5
XS Rating Curve= 0 ,0
Exp/Cntr=0.3,0.1

Type RM Length L Ch R = 1 ,10048   ,548,548,548
BEGIN DESCRIPTION:
Mapping XS 4a3154cf
END DESCRIPTION:
XS GIS Cut Line= 5
      2743637.27     10148434.43      2743897.67     10148395.37
      2744283.95     10148286.87      2744487.95     10148230.44
      2744612.21     10148166.17
#Sta/Elev= 30
    4647 1657.49  4690.3 1653.12  4759.3 1641.52  4817.3 1636.75  4867.9 1628.88
  4892.5 1627.74  4960.2 1619.73  5001.7 1607.29  5002.7 1605.84  5003.2 1605.34
  5015.3 1605.84  5051.6  1613.5  5082.4 1618.72  5188.7 1628.01    5229  1634.3
  5240.6 1637.62  5261.4 1638.38  5282.4 1641.65  5302.3 1645.88  5307.5 1644.16
  5309.8 1648.25  5341.8 1654.08  5375.6 1651.91  5415.7  1645.5  5455.2  1641.1
  5571.6 1633.02  5577.2 1634.29  5599.5 1633.37    5622 1636.44  5663.1 1638.58
#Mann= 5 ,-1 , 0
    4647     .05       0  5002.7     .05       0  5015.3     .05       0
  5051.6     .12       0  5282.4     .05       0
Bank Sta=5002.7,5015.3
XS Rating Curve= 0 ,0
Exp/Cntr=0.3,0.1

Type RM Length L Ch R = 1 ,9500    ,500,500,500
BEGIN DESCRIPTION:
BERNST CREEK 19.0
END DESCRIPTION:
XS GIS Cut Line= 3
      2743855.66     10148853.11      2744077.72     10148904.82
      2744455.66     10148403.15
#Sta/Elev= 30
    4772 1637.61  4843.9 1622.81  4864.4 1620.84  4886.2 1615.57  4915.8 1613.15
  4936.3 1609.69  4956.8 1608.31  4977.4 1605.45  5044.1 1602.01  5044.6 1601.51
  5056.7 1602.01  5064.7 1604.58  5071.2 1605.16  5077.5 1607.82  5090.6  1608.2
  5127.4 1610.98  5221.1 1613.16  5341.2 1621.86  5406.4 1626.32  5435.6 1626.89
  5441.8 1628.25  5464.7    1629  5506.4 1633.11  5520.9 1633.02  5564.6 1636.13
  5570.9 1635.58  5585.5  1637.3  5591.7 1636.87  5614.6 1639.19  5628.1 1639.37
#Mann= 5 ,-1 , 0
    4772     .05       0  5044.1     .03       0  5056.7     .05       0
  5090.6     .12       0  5341.2     .05       0
Bank Sta=5044.1,5056.7
XS Rating Curve= 0 ,0
Exp/Cntr=0.3,0.1

Type RM Length L Ch R = 1 ,9000    ,500,500,500
BEGIN DESCRIPTION:
BERNST CREEK 18.0
END DESCRIPTION:
XS GIS Cut Line= 3
      2743805.67      10149053.1      2744165.58      10149382.5
      2744405.67     10149203.12
#Sta/Elev= 30
  4512.1 1625.31  4639.5 1618.28  4724.6 1609.73  4788.1 1606.29  4795.5 1603.39
  4802.3    1605  4816.4 1605.34  4837.5    1604  4844.8 1599.92  4851.6  1601.1
  4887.4 1596.49  4894.1 1597.13  4901.5 1595.24  4915.7 1594.47  4922.5 1596.15
  4936.7 1596.51  4944.1 1593.61  4950.9 1595.62  4958.3 1592.71  4965.1 1593.32
  4966.1 1591.63  4966.6 1591.13  4978.8 1591.63  4979.2 1593.01  4986.6 1591.64
  5003.2 1592.13  5042.3 1595.43  5106.9 1604.85  5156.9 1609.97  5299.7 1617.98
#Mann= 3 ,-1 , 0
  4512.1     .05       0  4966.1     .05       0  4978.8     .05       0
Bank Sta=4966.1,4978.8
XS Rating Curve= 0 ,0
Exp/Cntr=0.3,0.1

Type RM Length L Ch R = 1 ,8500    ,500,500,500
BEGIN DESCRIPTION:
BERNST CREEK 17.0
END DESCRIPTION:
XS GIS Cut Line= 3
      2743405.73      10149803.1      2743890.96     10149694.24
      2744155.65      10149803.1
#Sta/Elev= 30
  4502.7 1614.14  4570.2 1608.07  4575.4 1609.11  4618.7 1607.04  4635.9 1604.41
  4710.5 1599.22  4753.8 1594.45  4797.2 1594.38  4810.1  1595.6  4840.5 1593.37
  4845.6 1594.55  4871.6  1588.6    4889 1587.95  4894.1 1590.05  4967.6 1584.12
  4968.1 1583.62  4980.5 1584.12  4985.9 1585.88  4994.6 1586.17  5039.7 1584.24
  5058.3  1586.3  5063.7 1588.82  5087.6 1590.49    5124  1597.1  5140.9    1602
  5146.4 1600.82  5188.9 1606.35  5223.6 1606.08  5271.6  1609.2  5286.2 1608.15
#Mann= 3 ,-1 , 0
  4502.7     .05       0  4967.6     .05       0  4980.5     .05       0
Bank Sta=4967.6,4980.5
XS Rating Curve= 0 ,0
Exp/Cntr=0.3,0.1

Type RM Length L Ch R = 1 ,8000    ,500,500,500
BEGIN DESCRIPTION:
BERNST CREEK 16.0
END DESCRIPTION:
XS GIS Cut Line= 3
      2743505.72     10150053.11      2743880.65     10150080.09
      2744105.69      10149903.1
#Sta/Elev= 30
  4624.1 1604.16  4644.1 1604.01  4664.2 1599.94  4684.2 1599.82  4691.5 1598.32
  4704.3 1600.29  4744.4 1594.41  4764.4 1594.34  4784.5 1592.41  4814.6 1586.71
  4824.6 1588.37  4831.3 1588.49  4836.3 1590.02  4844.6 1589.59  4864.7 1584.04
  4924.8 1573.88  4978.4 1571.55  4978.9 1571.05  4991.5 1571.55    5000  1572.3
    5008 1574.67  5057.7 1583.77  5080.2 1585.74  5165.2 1599.77  5194.1 1602.94
  5229.4  1604.3  5235.7 1603.24  5258.3  1604.1  5264.6 1603.25  5286.3  1603.8
#Mann= 3 ,-1 , 0
  4624.1     .05       0  4978.4     .05       0  4991.5     .05       0
Bank Sta=4978.4,4991.5
XS Rating Curve= 0 ,0
Exp/Cntr=0.3,0.1

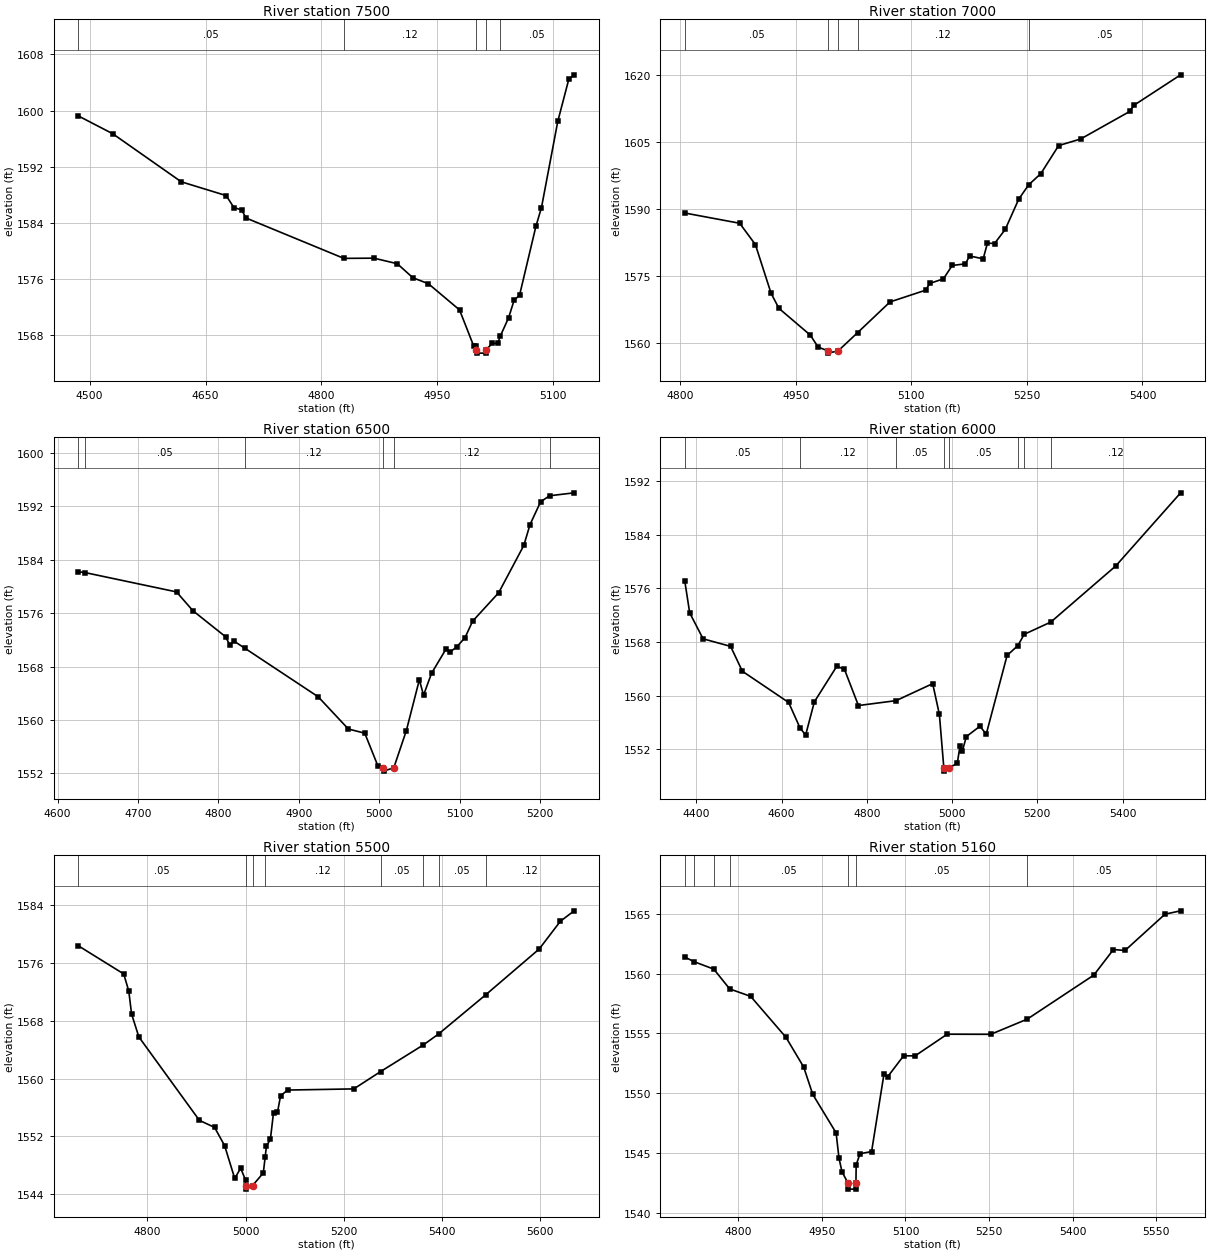
Type RM Length L Ch R = 1 ,7500    ,500,500,500
BEGIN DESCRIPTION:
BERNST CREEK 15.0
END DESCRIPTION:
XS GIS Cut Line= 3
       2743655.7     10150403.11      2744166.89     10150462.27
      2744255.66     10150553.09
#Sta/Elev= 30
  4485.4 1599.24  4529.8 1596.71  4618.6 1589.86  4676.7  1587.9  4686.7 1586.19
  4696.8 1585.86  4702.3 1584.71    4829 1578.96  4867.9 1578.99  4898.1  1578.2
  4918.3  1576.2  4938.4 1575.35  4978.7 1571.62  4996.9 1566.51    5000 1566.51
  5000.2 1565.97  5000.7 1565.47  5012.9 1565.47  5013.4 1565.97  5020.9 1566.87
  5028.1 1566.86  5031.5 1567.91  5042.2 1570.51  5049.2 1572.97  5056.4 1573.74
  5077.5 1583.52  5084.7 1586.19  5105.8 1598.46    5120 1604.44    5127 1605.09
#Mann= 5 ,-1 , 0
  4485.4     .05       0    4829     .12       0  5000.2     .07       0
  5013.4     .12       0  5031.5     .05       0
Bank Sta=5000.2,5013.4
XS Rating Curve= 0 ,0
Exp/Cntr=0.3,0.1

Type RM Length L Ch R = 1 ,7000    ,500,500,500
BEGIN DESCRIPTION:
BERNST CREEK 14.0
END DESCRIPTION:
XS GIS Cut Line= 3
      2743805.65      10150853.1      2743996.25     10150888.68
      2744405.67     10150703.12
#Sta/Elev= 30
  4806.1 1589.14  4877.3 1586.85  4897.7 1582.08    4918 1571.21  4928.2 1567.82
  4968.9 1561.84  4979.1 1559.16  4991.9  1558.3  4992.4  1557.8  5005.1  1558.3
  5030.4 1562.39  5072.4 1569.25  5118.6 1571.88  5124.1  1573.4  5141.7 1574.42
  5153.1 1577.41  5170.2 1577.77  5175.7 1579.54  5193.3 1578.89  5198.8  1582.4
    5208 1582.32  5221.9 1585.46  5239.5 1592.27  5252.5 1595.48  5268.1 1597.95
  5291.2 1604.22  5319.8  1605.7  5383.6 1611.87    5389 1613.25  5449.5 1620.05
#Mann= 5 ,-1 , 0
  4806.1     .05       0  4991.9     .05       0  5005.1     .05       0
  5030.4     .12       0  5252.5     .05       0
Bank Sta=4991.9,5005.1
XS Rating Curve= 0 ,0
Exp/Cntr=0.3,0.1

Type RM Length L Ch R = 1 ,6500    ,500,500,500
BEGIN DESCRIPTION:
BERNST CREEK 13.0
END DESCRIPTION:
XS GIS Cut Line= 3
      2743855.72     10151253.12      2744223.42     10151322.55
      2744455.66     10151253.12
#Sta/Elev= 30
  4625.8 1582.21  4634.4 1582.08  4747.9 1579.19  4768.2 1576.38  4808.9 1572.47
  4814.2 1571.22  4819.3 1571.82  4832.5 1570.78  4924.1 1563.47  4961.6 1558.64
    4982 1558.02  4998.6 1553.03  5004.9 1552.83  5005.4 1552.33  5018.1 1552.83
  5033.7  1558.4  5049.9 1566.02  5055.1 1563.71    5065 1566.98    5083 1570.62
  5088.2  1570.2  5096.3 1570.94  5106.7 1572.34  5116.1  1574.8  5148.5 1579.06
  5179.8 1586.16  5187.5 1589.28  5200.7  1592.7  5211.8  1593.6  5242.4 1594.04
#Mann= 6 ,-1 , 0
  4625.8     .12       0  4634.4     .05       0  4832.5     .12       0
  5004.9     .07       0  5018.1     .12       0  5211.8     .05       0
Bank Sta=5004.9,5018.1
XS Rating Curve= 0 ,0
Exp/Cntr=0.3,0.1

Type RM Length L Ch R = 1 ,6000    ,500,500,500
BEGIN DESCRIPTION:
BERNST CREEK 12.0
END DESCRIPTION:
XS GIS Cut Line= 3
      2743674.72     10151998.64      2744274.04     10151814.76
      2744778.88     10151634.06
#Sta/Elev= 30
  4373.1 1577.08  4384.6 1572.35    4416 1568.48  4480.6 1567.35  4508.1 1563.64
  4616.7 1558.98    4643 1555.23  4656.5  1554.1    4677 1559.07  4729.8  1564.4
  4747.7 1563.91  4780.4 1558.52  4868.6 1559.25  4954.6 1561.79  4970.3 1557.19
  4980.7 1549.23  4981.2 1548.73  4993.9 1549.23  5012.4 1549.92  5018.7 1552.54
    5024 1551.69  5033.6 1553.89  5065.5 1555.43  5080.2 1554.25  5129.2 1566.01
  5154.4 1567.46  5169.2 1569.15  5231.7 1570.98  5384.1 1579.36  5536.2 1590.27
#Mann= 8 ,-1 , 0
  4373.1     .05       0    4643     .12       0  4868.6     .05       0
  4980.7     .05       0  4993.9     .05       0  5154.4     .12       0
  5169.2     .05       0  5231.7     .12       0
Bank Sta=4980.7,4993.9
XS Rating Curve= 0 ,0
Exp/Cntr=0.3,0.1

Type RM Length L Ch R = 1 ,5500    ,340,340,340
BEGIN DESCRIPTION:
BERNST CREEK 11.0
END DESCRIPTION:
XS GIS Cut Line= 3
      2744055.72      10152353.1      2744387.25     10152275.03
      2744805.66     10151753.15
#Sta/Elev= 30
  4659.4 1578.41  4751.8 1574.51  4762.1 1572.14  4767.8 1568.97  4782.6 1565.79
  4905.9 1554.23  4936.8 1553.26  4957.3 1550.72  4977.8 1546.19  4989.9 1547.61
    5000 1545.94  5000.1 1545.21  5000.6 1544.71  5014.2 1545.21    5036 1546.95
  5039.8 1549.16  5042.4 1550.68  5050.4  1551.6  5056.8 1555.31  5064.8 1555.33
  5071.2 1557.64  5085.6 1558.43  5220.3 1558.59  5274.8 1560.99  5361.6 1564.67
  5392.8 1566.19    5489 1571.63  5597.7 1577.96  5640.9 1581.81  5668.9 1583.25
#Mann= 8 ,-1 , 0
  4659.4     .05       0  5000.1     .05       0  5014.2     .05       0
  5039.8     .12       0  5274.8     .05       0  5361.6     .12       0
  5392.8     .05       0    5489     .12       0
Bank Sta=5000.1,5014.2
XS Rating Curve= 0 ,0
Exp/Cntr=0.3,0.1

Type RM Length L Ch R = 1 ,5160    ,585,585,585
BEGIN DESCRIPTION:
BERNST CREEK 10.0
END DESCRIPTION:
XS GIS Cut Line= 3
       2744247.6      10152654.9      2744528.75       10152562.
      2744905.72     10152103.07
#Sta/Elev= 30
  4703.9 1561.39  4720.1 1561.01  4755.9 1560.38  4784.5 1558.72  4822.1  1558.1
  4885.5 1554.67  4917.3 1552.18  4933.6 1549.89  4975.5 1546.67  4980.7 1544.54
  4986.2 1543.39    4997 1542.46  4997.5 1541.96  5010.6 1541.96  5011.1 1542.46
  5011.5 1543.99  5018.4 1544.92  5039.2 1545.11  5061.4 1551.59  5067.9 1551.36
  5096.6 1553.12  5117.4 1553.12  5174.8 1554.93    5253 1554.92  5318.5 1556.19
  5438.1 1559.88  5473.3 1562.02  5494.1 1561.94  5565.9 1564.98  5593.9 1565.26
#Mann= 7 ,-1 , 0
  4703.9     .12       0  4720.1     .05       0  4755.9     .12       0
  4784.5     .05       0    4997     .05       0  5011.1     .05       0
  5318.5     .05       0
Bank Sta=4997,5011.1
XS Rating Curve= 0 ,0
Exp/Cntr=0.3,0.1

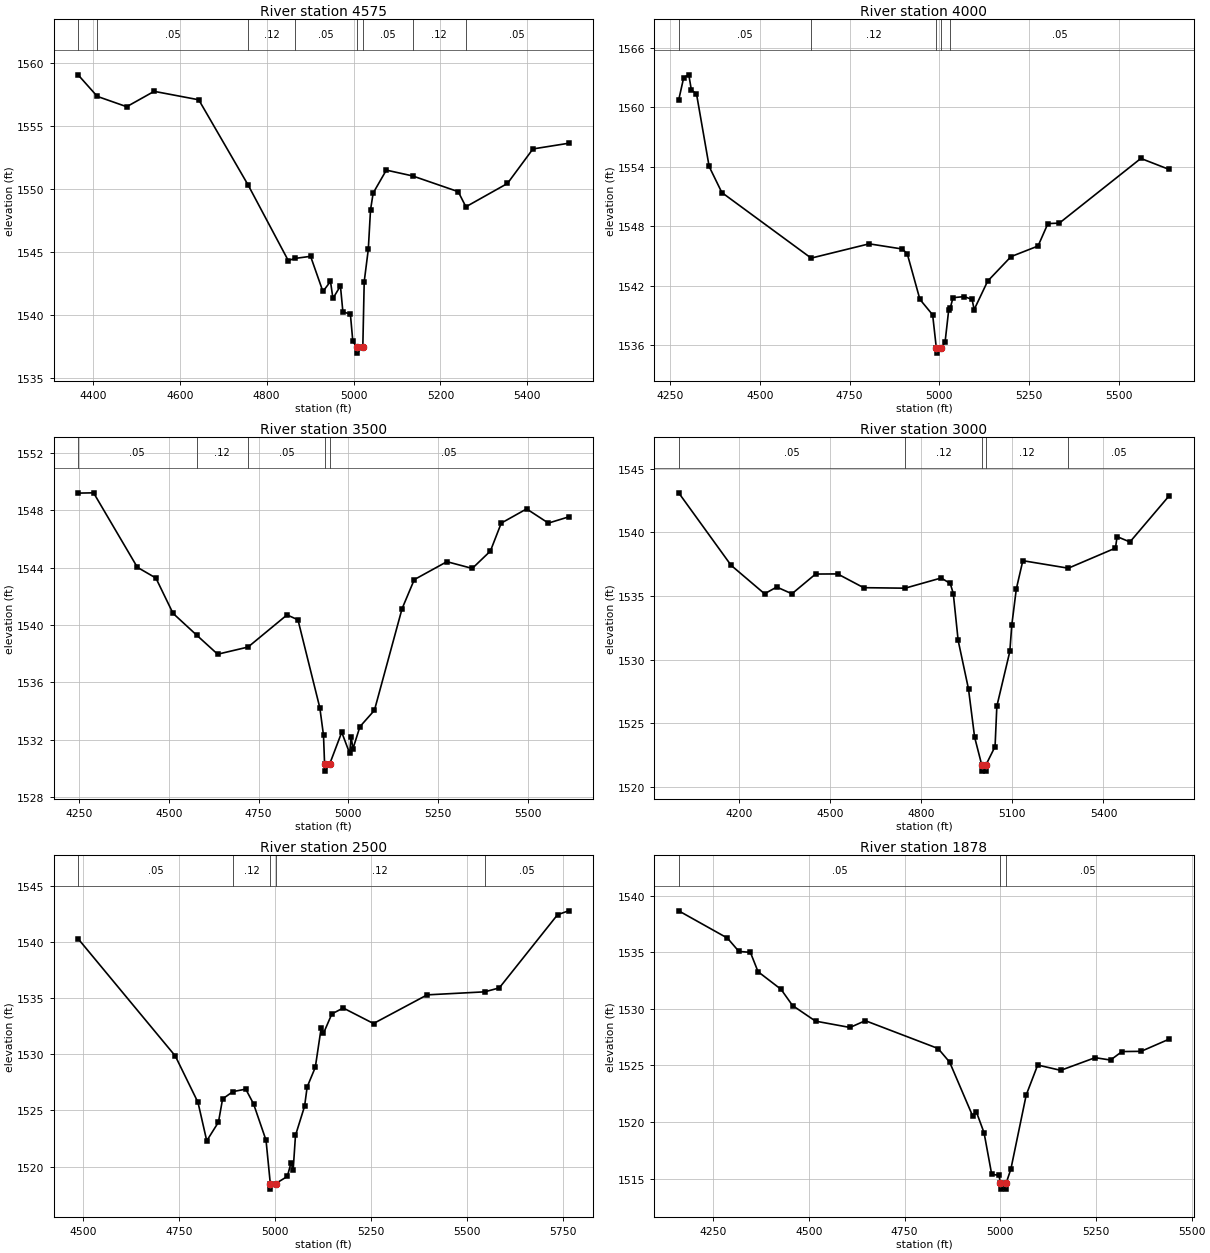
Type RM Length L Ch R = 1 ,4575    ,575,575,575
BEGIN DESCRIPTION:
BERNST CREEK 9.0
END DESCRIPTION:
XS GIS Cut Line= 3
      2744226.74     10152712.17      2744801.75       10152979.
      2745282.33     10153097.18
#Sta/Elev= 30
  4366.1 1559.03  4410.3 1557.32    4478  1556.5  4541.2 1557.72  4643.8 1557.05
  4757.7 1550.27  4849.9 1544.29  4864.4 1544.46  4901.2 1544.63  4929.6 1541.84
    4947 1542.64  4952.6 1541.29  4969.9 1542.28  4975.5 1540.23  4992.8 1540.04
  4998.4 1537.88  5007.2 1537.45  5007.7 1536.95  5021.4 1537.45  5024.6 1542.62
    5034 1545.18  5039.1 1548.31  5045.2 1549.65  5075.5 1551.47  5135.8 1551.01
  5240.9 1549.76  5258.6 1548.56  5354.2 1550.41  5412.9 1553.15  5494.9  1553.6
#Mann= 8 ,-1 , 0
  4366.1     .12       0  4410.3     .05       0  4757.7     .12       0
  4864.4     .05       0  5007.2     .05       0  5021.4     .05       0
  5135.8     .12       0  5258.6     .05       0
Bank Sta=5007.2,5021.4
XS Rating Curve= 0 ,0
Exp/Cntr=0.3,0.1

Type RM Length L Ch R = 1 ,4000    ,500,500,500
BEGIN DESCRIPTION:
BERNST CREEK 8.0
END DESCRIPTION:
XS GIS Cut Line= 3
      2744005.69     10152853.12      2744512.56     10153372.75
      2745070.56     10153686.17
#Sta/Elev= 30
  4274.1 1560.73  4288.1    1563  4302.3 1563.27  4309.5 1561.72  4323.6 1561.38
  4358.9 1554.03  4394.3  1551.4    4643 1544.79  4804.5 1546.23  4896.4 1545.71
  4910.5 1545.24  4945.8 1540.63  4981.3 1539.07  4991.6 1535.71  4992.1 1535.21
  5005.8 1535.71  5015.9 1536.32  5026.1 1539.59  5030.4 1539.77    5038  1540.8
  5069.4 1540.91  5091.1 1540.62  5096.9  1539.6  5134.5 1542.47  5199.5 1544.94
  5274.8 1546.01  5302.2 1548.27  5334.1 1548.32  5561.1 1554.84    5640 1553.73
#Mann= 5 ,-1 , 0
  4274.1     .05       0    4643     .12       0  4991.6     .07       0
  5005.8     .12       0  5030.4     .05       0
Bank Sta=4991.6,5005.8
XS Rating Curve= 0 ,0
Exp/Cntr=0.3,0.1

Type RM Length L Ch R = 1 ,3500    ,500,500,500
BEGIN DESCRIPTION:
BERNST CREEK 7.0
END DESCRIPTION:
XS GIS Cut Line= 3
      2743513.22     10153639.27      2744253.84      10153776.9
      2744861.45     10153863.12
#Sta/Elev= 30
  4246.7  1549.2  4289.9 1549.22  4411.9 1544.03  4463.6 1543.28  4511.3 1540.82
  4576.8 1539.31  4635.7 1537.97  4720.5 1538.47    4829 1540.71  4859.5 1540.37
  4920.5 1534.23  4930.7 1532.32  4933.7 1530.32  4934.2 1529.82    4948 1530.32
  4981.5 1532.53  5003.5 1531.07  5007.8  1532.2  5012.8 1531.38  5032.2 1532.92
  5072.6 1534.06  5149.6 1541.14  5183.7 1543.17  5274.6 1544.42  5345.3 1543.95
  5395.8 1545.16  5426.1 1547.11  5496.8  1548.1  5557.4 1547.11  5613.7 1547.54
#Mann= 5 ,-1 , 0
  4246.7     .05       0  4576.8     .12       0  4720.5     .05       0
  4933.7     .05       0    4948     .05       0
Bank Sta=4933.7,4948
XS Rating Curve= 0 ,0
Exp/Cntr=0.3,0.1

Type RM Length L Ch R = 1 ,3000    ,500,500,500
BEGIN DESCRIPTION:
BERNST CREEK 6.0
END DESCRIPTION:
XS GIS Cut Line= 3
       2743273.6     10154337.19      2744269.75     10154273.15
       2744846.6     10154055.92
#Sta/Elev= 30
  4001.8 1543.11  4174.2 1537.42  4284.5 1535.18  4324.5 1535.71  4374.6 1535.18
  4452.4 1536.73    4525 1536.74  4610.5 1535.66  4747.1 1535.62  4865.7 1536.42
  4895.7 1535.99  4905.7  1535.2  4921.7 1531.52  4955.8  1527.7  4975.9 1523.92
  4999.2 1521.75  4999.7 1521.25    5013 1521.25  5013.5 1521.75  5043.2 1523.18
  5049.1 1526.35  5091.8 1530.65  5098.3 1532.73  5113.2 1535.56  5134.6 1537.78
  5284.3 1537.19  5439.5 1538.77  5444.9 1539.67  5487.2 1539.25  5616.4 1542.88
#Mann= 5 ,-1 , 0
  4001.8     .05       0  4747.1     .12       0  4999.2     .07       0
  5013.5     .12       0  5284.3     .05       0
Bank Sta=4999.2,5013.5
XS Rating Curve= 0 ,0
Exp/Cntr=0.3,0.1

Type RM Length L Ch R = 1 ,2500    ,622,622,622
BEGIN DESCRIPTION:
BERNST CREEK 5.0
END DESCRIPTION:
XS GIS Cut Line= 3
      2743805.71     10154853.11      2744310.72      10154763.5
      2744955.72     10154353.09
#Sta/Elev= 30
  4487.1 1540.29  4740.3 1529.85  4799.4 1525.72  4822.2  1522.3  4852.7 1523.96
  4863.5 1526.03  4890.4 1526.68  4923.8  1526.9  4944.1 1525.59  4976.6 1522.35
  4987.7  1518.5  4988.2    1518    5002  1518.5  5032.1 1519.13  5041.4 1520.31
  5047.3 1519.72  5053.3 1522.78    5077 1525.38  5083.7 1527.09  5104.9 1528.84
  5120.1 1532.32  5126.1 1531.86  5148.1  1533.6  5177.7 1534.12  5256.5 1532.74
  5396.2 1535.29    5546 1535.56  5584.1 1535.91  5735.7 1542.42  5764.5 1542.77
#Mann= 5 ,-1 , 0
  4487.1     .05       0  4890.4     .12       0  4987.7     .07       0
    5002     .12       0    5546     .05       0
Bank Sta=4987.7,5002
XS Rating Curve= 0 ,0
Exp/Cntr=0.3,0.1

Type RM Length L Ch R = 1 ,1878    ,402,402,402
BEGIN DESCRIPTION:
Mapping XS 90ae13d0
END DESCRIPTION:
XS GIS Cut Line= 2
      2743398.51      10155326.8      2744678.92     10155374.54
#Sta/Elev= 30
    4160 1538.67  4287.3 1536.26  4317.3 1535.08  4347.3    1535  4367.3 1533.29
  4427.4 1531.73  4457.4  1530.3  4517.4 1528.92  4607.5 1528.36  4647.5 1528.96
  4837.6  1526.5  4867.7  1525.3  4927.7 1520.55  4937.7 1520.89  4957.7 1519.05
  4977.7 1515.37  4996.6  1515.3  5000.5 1514.57    5001 1514.07  5014.6 1514.07
  5015.1 1514.57  5027.8 1515.85  5067.8 1522.39  5097.8 1525.04  5157.9 1524.57
  5247.9 1525.69    5288 1525.48    5318 1526.23    5368 1526.25  5441.3 1527.33
#Mann= 3 ,-1 , 0
    4160     .05       0  5000.5     .05       0  5015.1     .05       0
Bank Sta=5000.5,5015.1
XS Rating Curve= 0 ,0
Exp/Cntr=0.3,0.1

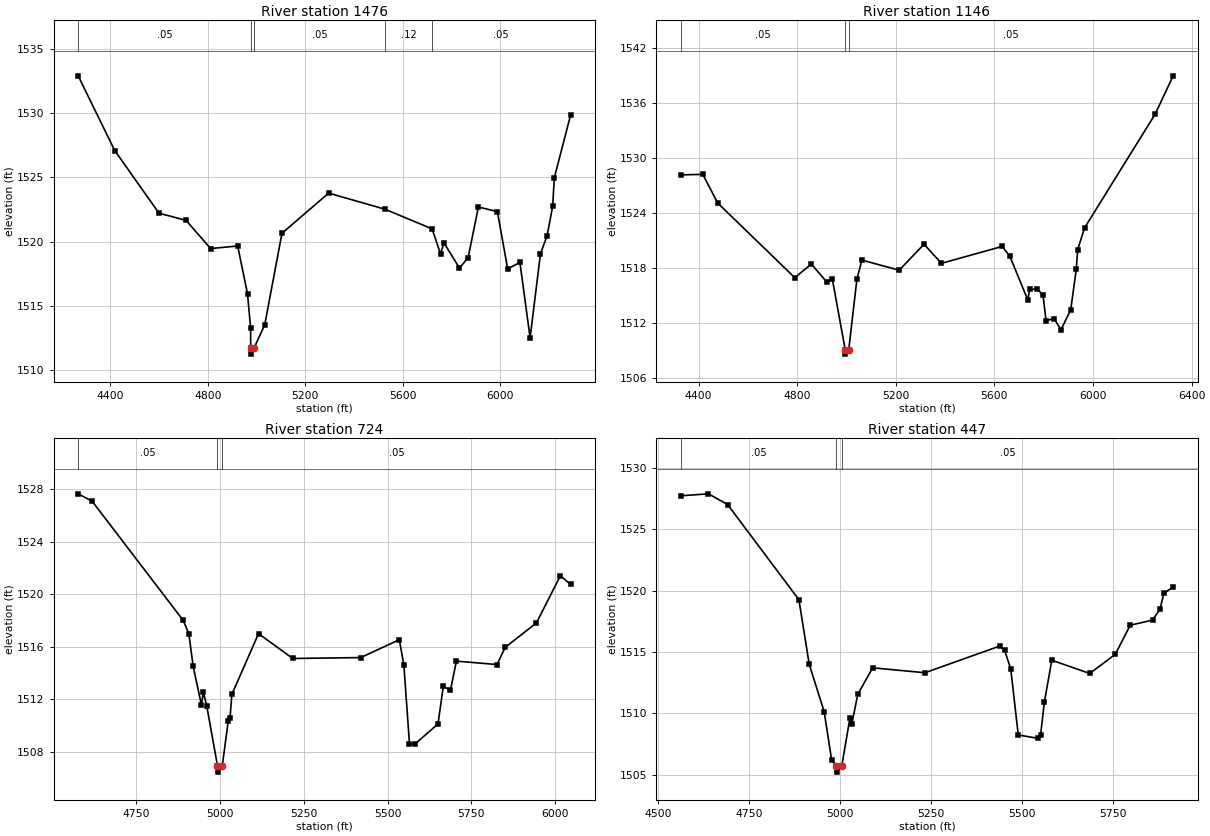
Type RM Length L Ch R = 1 ,1476    ,330,330,330
BEGIN DESCRIPTION:
Mapping XS af915639
END DESCRIPTION:
XS GIS Cut Line= 3
        2743507.     10155647.97      2744735.08     10155823.98
      2745320.67      10156341.9
#Sta/Elev= 30
  4267.5 1532.89  4417.7 1527.08  4599.5 1522.21  4710.7 1521.65  4811.7 1519.46
  4922.8 1519.66  4963.2 1515.93  4975.9 1513.28  4976.1 1511.75  4976.6 1511.25
  4990.7 1511.75  5033.9 1513.53  5104.7 1520.65  5296.6 1523.77  5527.5 1522.52
  5721.4 1520.99  5755.9 1519.05  5770.1 1519.91  5833.7 1517.94  5869.4 1518.75
  5911.5 1522.69  5989.5 1522.33  6031.9 1517.88  6082.1 1518.38  6123.9 1512.52
  6166.6 1519.06  6193.6 1520.44  6216.5 1522.73  6223.5 1524.97  6289.9 1529.81
#Mann= 5 ,-1 , 0
  4267.5     .05       0  4976.1     .05       0  4990.7     .05       0
  5527.5     .12       0  5721.4     .05       0
Bank Sta=4976.1,4990.7
XS Rating Curve= 0 ,0
Exp/Cntr=0.3,0.1

Type RM Length L Ch R = 1 ,1146    ,422,422,422
BEGIN DESCRIPTION:
Mapping XS e5463613
END DESCRIPTION:
XS GIS Cut Line= 3
      2743507.08     10155990.86      2744650.62     10156136.76
      2745408.26     10156508.89
#Sta/Elev= 30
    4328 1528.14  4417.3  1528.2  4477.8 1525.07  4790.3 1516.95  4857.6 1518.43
  4921.4 1516.43  4942.5 1516.82  4994.7 1509.12  4995.2 1508.62  5009.3 1509.12
  5042.3 1516.79  5062.5 1518.86  5213.7 1517.76  5314.5 1520.59  5385.1 1518.51
  5631.3 1520.35  5662.2  1519.3  5735.3 1514.53  5742.7 1515.66  5774.6 1515.73
  5797.1 1515.03  5809.5 1512.27  5842.1 1512.48  5870.1 1511.28  5909.5 1513.45
    5932 1517.85  5937.6 1519.99  5965.6 1522.37  6252.3 1534.77  6324.9 1538.93
#Mann= 3 ,-1 , 0
    4328     .05       0  4994.7     .05       0  5009.3     .05       0
Bank Sta=4994.7,5009.3
XS Rating Curve= 0 ,0
Exp/Cntr=0.3,0.1

Type RM Length L Ch R = 1 ,724     ,277,277,277
BEGIN DESCRIPTION:
Mapping XS 231e375c
END DESCRIPTION:
XS GIS Cut Line= 2
      2743606.83     10156307.68      2744980.66      10156828.1
#Sta/Elev= 30
  4576.9 1527.63  4618.5 1527.07  4889.9 1518.02  4907.2 1516.99    4920 1514.52
  4944.8 1511.57  4950.2 1512.56  4960.6  1511.5  4992.5 1506.97    4993 1506.47
  5007.1 1506.97  5024.6 1510.34    5030 1510.56  5035.5 1512.38  5115.1    1517
  5217.3 1515.11    5420 1515.18  5535.3 1516.54  5548.8  1514.6  5565.5 1508.64
  5580.9 1508.59  5650.6 1510.13  5666.4 1512.99  5687.8  1512.7  5705.6 1514.91
  5826.8 1514.65    5851 1515.95  5944.4 1517.82  6015.9 1521.41    6046 1520.74
#Mann= 3 ,-1 , 0
  4576.9     .05       0  4992.5     .05       0  5007.1     .05       0
Bank Sta=4992.5,5007.1
XS Rating Curve= 0 ,0
Exp/Cntr=0.3,0.1

Type RM Length L Ch R = 1 ,447     ,0,0,0
BEGIN DESCRIPTION:
BERNST CREEK 4.0
END DESCRIPTION:
XS GIS Cut Line= 3
      2743630.66      10156578.1      2743928.05       10156707.
      2744930.73     10156928.12
#Sta/Elev= 30
  4563.3 1527.72  4639.2 1527.88  4691.6 1527.01  4887.4 1519.25  4915.7 1513.98
  4956.7 1510.13  4977.2 1506.18  4990.4  1505.7  4990.9  1505.2    5005  1505.7
  5027.6 1509.65  5032.7 1509.14  5048.9 1511.54  5089.8  1513.7  5233.2  1513.3
    5438 1515.47  5451.6 1515.15  5468.7  1513.6  5489.2 1508.23  5544.1 1507.95
  5550.6 1508.25  5560.9 1510.92  5581.3 1514.32  5685.4 1513.24  5755.4  1514.8
  5796.4 1517.17  5857.8 1517.59  5878.3  1518.5  5888.6 1519.76  5914.2 1520.29
#Mann= 3 ,-1 , 0
  4563.3     .05       0  4990.4     .03       0    5005     .05       0
Bank Sta=4990.4,5005
XS Rating Curve= 0 ,0
Exp/Cntr=0.3,0.1

Chan Stop Cuts=-1
Use User Specified Reach Order=0
Composite Channel Slope=5