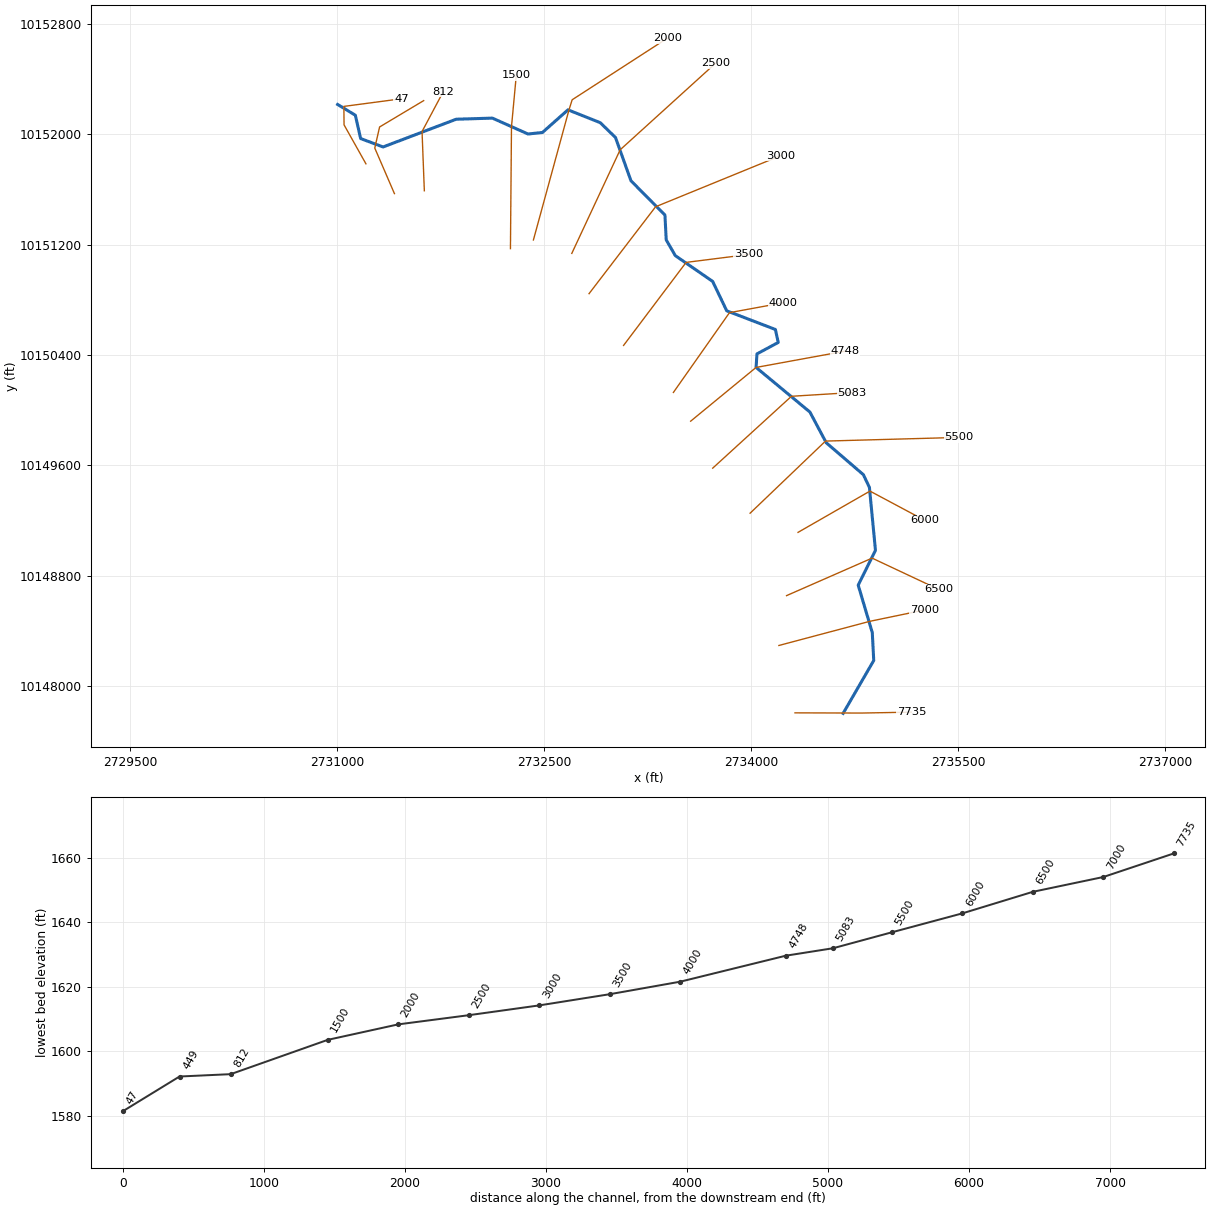
--- BLOCKHOUSE CREEK.prj (project) ---

Proj Title=BLOCKHOUSE CREEK Base Level Engineering
Current Plan=p01
Default Exp/Contr=0.3,0.1
English Units
Geom File=g01
Flow File=f01
Plan File=p01
Y Axis Title=Elevation
X Axis Title(PF)=Main Channel Distance
X Axis Title(XS)=Station
BEGIN DESCRIPTION:
BLOCKHOUSE CREEK
END DESCRIPTION:
DSS Export Rating Curves= 0
DSS Export Rating Curve Sorted= 0
DSS Export Volume Flow Curves= 0
DXF OffsetX= 0
DXF OffsetY= 0
DXF ScaleX= 1
DXF ScaleY= 10

--- BLOCKHOUSE CREEK.p01 (plan) ---

Plan Title=Multiple Run
Short Identifier=Multiple
Geom File=g01
Flow File=f01
Subcritical Flow
K Sum by GR= 0
Std Step Tol= 0.01
Critical Tol= 0.01
Num of Std Step Trials= 20
Max Error Tol= 0.3
Flow Tol Ratio= 0.001
Split Flow NTrial= 30
Split Flow Tol= 0.02
Split Flow Ratio= 0.02
Log Output Level= 0
Friction Slope Method= 1
Unsteady Friction Slope Method= 2
Unsteady Bridges Friction Slope Method= 1
Parabolic Critical Depth
Global Vel Dist=  1 , 1 , 1
Global Log Level= 0
CheckData=True
Encroach Param= -1, 0, 0, 0
BEGIN DESCRIPTION:
Multiple Run
END DESCRIPTION:

--- BLOCKHOUSE CREEK.f01 (steady flow) ---

Flow Title=Multiple
Program Version=4.10
Number of Profiles= 7
Profile Names=10-year,25-year,50-year,1pct_min,100-year,1pct_plu,500-year
River Rch & RM=BLOCKHOUSE CREEK,Reach-1         ,7735
     859    1467    2637    1870    3740    7481    5365
Boundary for River Rch & Prof#=BLOCKHOUSE CREEK,Reach-1         , 1
Up Type= 0
Dn Type= 3
Dn Slope=0.005
Boundary for River Rch & Prof#=BLOCKHOUSE CREEK,Reach-1         , 2
Up Type= 0
Dn Type= 3
Dn Slope=0.005
Boundary for River Rch & Prof#=BLOCKHOUSE CREEK,Reach-1         , 3
Up Type= 0
Dn Type= 3
Dn Slope=0.005
Boundary for River Rch & Prof#=BLOCKHOUSE CREEK,Reach-1         , 4
Up Type= 0
Dn Type= 3
Dn Slope=0.005
Boundary for River Rch & Prof#=BLOCKHOUSE CREEK,Reach-1         , 5
Up Type= 0
Dn Type= 3
Dn Slope=0.005
Boundary for River Rch & Prof#=BLOCKHOUSE CREEK,Reach-1         , 6
Up Type= 0
Dn Type= 3
Dn Slope=0.005
Boundary for River Rch & Prof#=BLOCKHOUSE CREEK,Reach-1         , 7
Up Type= 0
Dn Type= 3
Dn Slope=0.005
DSS Import GetInterval= 0
DSS Import GetPeak= 0
DSS Import FillOption= 0

--- BLOCKHOUSE CREEK.g01 (geometry) ---

Geom Title=Existing Conditions
Program Version=4.10

River Reach=BLOCKHOUSE CREEK,Reach-1
Reach XY= 30
      2734665.75       10147804.       2734887.5       10148187.
        2734877.       10148389.        2734775.       10148733.
        2734900.       10148985.      2734856.25       10149441.
       2734812.5       10149533.      2734543.75       10149764.
        2734425.       10149987.      2734035.25       10150310.
       2734041.5       10150408.      2734195.75       10150491.
        2734175.       10150585.      2733822.75       10150720.
      2733720.75       10150933.        2733450.       10151120.
      2733384.25       10151234.        2733375.       10151414.
        2733129.       10151662.       2733016.5       10151976.
      2732906.25       10152083.      2732672.75       10152176.
       2732487.5       10152012.      2732383.25       10152001.
        2732125.       10152116.       2731862.5       10152108.
      2731333.25       10151907.      2731170.75       10151968.
      2731132.25       10152137.        2731004.       10152215.

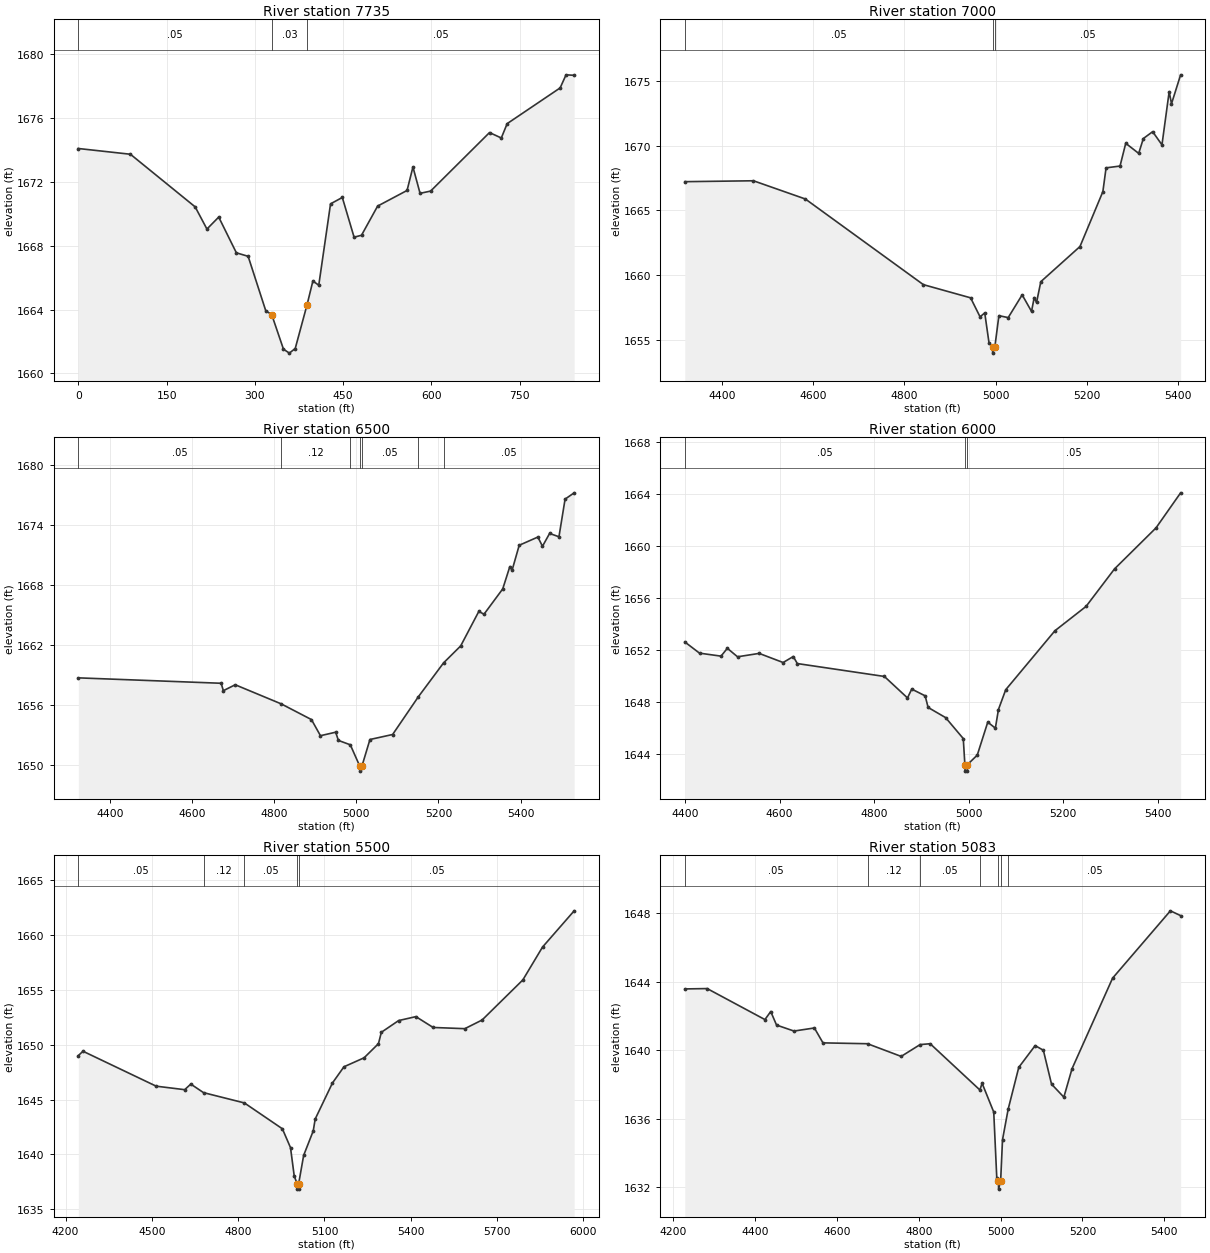
Type RM Length L Ch R = 1 ,7735    ,500,500,500
BEGIN DESCRIPTION:
BLOCKHOUSE CREEK 15.0
END DESCRIPTION:
XS GIS Cut Line= 3
      2734317.16     10147807.78      2734795.93     10147806.32
      2735159.46     10147812.91
#Sta/Elev= 30
       0  1674.1    88.5 1673.74   198.5 1670.44   218.5 1669.05   238.5  1669.8
   268.5 1667.56   288.5 1667.34   318.5 1663.92   328.5 1663.69   348.5 1661.52
   358.5 1661.27   368.5 1661.56   388.5 1664.29   398.5 1665.79   408.5 1665.53
   428.5 1670.63   448.5 1671.03   468.5 1668.54   481.1 1668.66   508.5 1670.49
   558.5 1671.47   568.5 1672.94   580.6 1671.29   598.5 1671.43   698.6  1675.1
   718.6 1674.76   728.6 1675.66   818.6  1677.9   828.6 1678.72   842.4 1678.69
#Mann= 3 , 0 , 0
       0     .05       0   328.5     .03       0   388.5     .05       0
Bank Sta=328.5,388.5
XS Rating Curve= 0 ,0
Exp/Cntr=0.3,0.1

Type RM Length L Ch R = 1 ,7000    ,500,500,500
BEGIN DESCRIPTION:
BLOCKHOUSE CREEK 14.0
END DESCRIPTION:
XS GIS Cut Line= 3
      2734200.32     10148295.79      2734858.57     10148470.72
      2735255.71     10148553.12
#Sta/Elev= 30
  4318.9 1667.23  4469.3  1667.3  4583.1 1665.89  4841.8 1659.26  4945.3 1658.24
    4966 1656.77  4976.3 1657.07  4985.7 1654.74  4993.3 1654.46  4993.7 1653.96
  4998.5 1654.46  5007.3 1656.86  5027.7 1656.71  5058.3 1658.47  5078.8 1657.19
  5084.7 1658.26  5089.8 1657.88  5099.2 1659.49    5185 1662.21  5235.2 1666.46
  5242.2  1668.3  5272.8 1668.44  5285.3  1670.2  5313.7 1669.42  5323.9 1670.57
  5344.3  1671.1  5364.7 1670.08  5380.5  1674.2  5385.6 1673.26  5405.6  1675.5
#Mann= 3 ,-1 , 0
  4318.9     .05       0  4993.3     .05       0  4998.5     .05       0
Bank Sta=4993.3,4998.5
XS Rating Curve= 0 ,0
Exp/Cntr=0.3,0.1

Type RM Length L Ch R = 1 ,6500    ,500,500,500
BEGIN DESCRIPTION:
BLOCKHOUSE CREEK 13.0
END DESCRIPTION:
XS GIS Cut Line= 3
      2734255.86      10148656.9      2734875.58     10148928.69
      2735355.72     10148703.09
#Sta/Elev= 30
  4323.3 1658.69    4671 1658.15  4676.4 1657.41  4705.3    1658  4817.3 1656.09
  4890.9 1654.52  4912.8 1652.91  4949.9 1653.26  4956.4 1652.44  4985.5    1652
  5008.5 1649.87  5008.9 1649.37  5013.8 1649.87  5033.3 1652.53  5088.5 1653.03
  5150.8 1656.78  5212.6 1660.19  5254.2 1661.88  5298.4 1665.33    5311 1665.05
  5356.6 1667.58  5373.9 1669.81  5379.5 1669.46  5396.7 1671.94  5442.1 1672.76
  5453.4 1671.84  5470.7 1673.12  5493.5 1672.79  5508.4 1676.55  5530.5 1677.18
#Mann= 7 ,-1 , 0
  4323.3     .05       0  4817.3     .12       0  4985.5     .05       0
  5008.5     .05       0  5013.8     .05       0  5150.8     .12       0
  5212.6     .05       0
Bank Sta=5008.5,5013.8
XS Rating Curve= 0 ,0
Exp/Cntr=0.3,0.1

Type RM Length L Ch R = 1 ,6000    ,500,500,500
BEGIN DESCRIPTION:
BLOCKHOUSE CREEK 12.0
END DESCRIPTION:
XS GIS Cut Line= 3
      2734339.22     10149115.25      2734860.25      10149414.2
      2735255.64     10149203.13
#Sta/Elev= 30
  4399.3 1652.61  4430.4 1651.75  4475.9 1651.52  4489.3 1652.12  4510.9 1651.47
  4556.6 1651.73  4607.3 1651.03  4628.8 1651.49  4637.3 1650.95  4821.5 1649.96
  4870.4 1648.31  4879.4 1648.99  4907.8 1648.47    4914 1647.58    4951  1646.8
  4988.4 1645.19  4991.8 1643.19  4992.2 1642.69  4996.8 1642.69  4997.2 1643.19
    5018 1643.92  5040.2 1646.45  5056.3 1645.99  5062.8 1647.42  5078.2 1648.94
  5182.3 1653.47  5248.2 1655.34  5308.4 1658.22  5396.2 1661.37  5448.2 1664.06
#Mann= 3 ,-1 , 0
  4399.3     .05       0  4991.8     .05       0  4997.2     .05       0
Bank Sta=4991.8,4997.2
XS Rating Curve= 0 ,0
Exp/Cntr=0.3,0.1

Type RM Length L Ch R = 1 ,5500    ,417,417,417
BEGIN DESCRIPTION:
BLOCKHOUSE CREEK 11.0
END DESCRIPTION:
XS GIS Cut Line= 3
      2733991.96     10149254.11      2734538.05     10149776.48
      2735505.69     10149803.11
#Sta/Elev= 30
  4244.3 1649.01  4260.5 1649.41  4514.9 1646.22    4614  1645.9  4635.3 1646.41
  4679.5 1645.63  4821.6 1644.69  4953.6 1642.33  4981.9 1640.61  4994.9 1638.01
  5004.9 1637.32  5005.3 1636.82  5009.9 1636.82  5010.3 1637.32  5027.6  1639.9
    5061 1642.14  5067.7 1643.22  5127.7 1646.51  5167.7 1647.99  5237.7 1648.81
  5287.7  1650.1  5297.7 1651.14  5357.8 1652.21  5417.8 1652.57  5477.8 1651.58
  5587.9 1651.47  5647.9 1652.26  5789.6 1655.92    5858 1658.92    5968 1662.23
#Mann= 5 ,-1 , 0
  4244.3     .05       0  4679.5     .12       0  4821.6     .05       0
  5004.9     .05       0  5010.3     .05       0
Bank Sta=5004.9,5010.3
XS Rating Curve= 0 ,0
Exp/Cntr=0.3,0.1

Type RM Length L Ch R = 1 ,5083    ,335,335,335
BEGIN DESCRIPTION:
BLOCKHOUSE CREEK 10.0
END DESCRIPTION:
XS GIS Cut Line= 3
      2733721.11     10149580.48       2734291.5       10150101.
      2734730.66     10150128.11
#Sta/Elev= 30
  4227.8 1643.57  4282.5 1643.59  4423.7 1641.78  4437.9 1642.25  4452.1 1641.46
  4494.7 1641.11  4544.6 1641.29  4565.6 1640.42  4674.5 1640.37  4756.8 1639.63
  4803.1 1640.32  4827.7 1640.37  4949.2 1637.67  4954.7 1638.06  4983.1 1636.38
  4990.5 1632.55  4994.6 1632.38    4995 1631.88    5000 1632.38  5004.6 1634.77
  5018.4 1636.55  5044.3 1638.99  5084.3 1640.26  5104.4 1639.99  5124.4 1638.01
  5154.5 1637.25  5174.5 1638.91  5273.7  1644.2    5415 1648.13    5440 1647.85
#Mann= 7 ,-1 , 0
  4227.8     .05       0  4674.5     .12       0  4803.1     .05       0
  4949.2     .12       0  4994.6     .07       0    5000     .12       0
  5018.4     .05       0
Bank Sta=4994.6,5000
XS Rating Curve= 0 ,0
Exp/Cntr=0.3,0.1

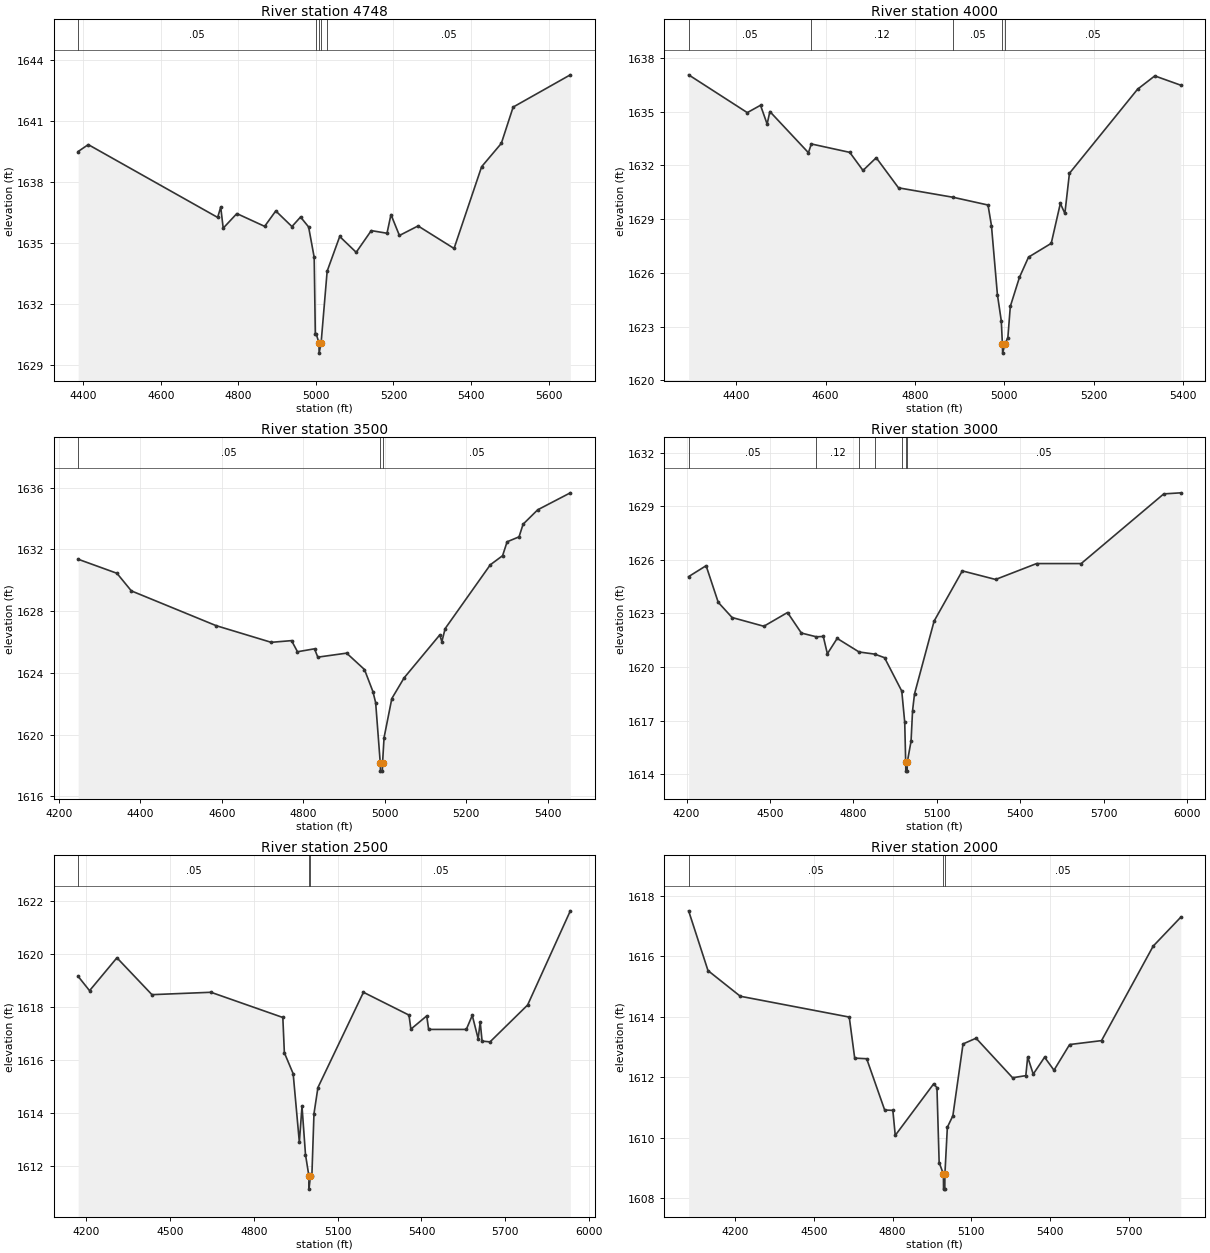
Type RM Length L Ch R = 1 ,4748    ,748,748,748
BEGIN DESCRIPTION:
BLOCKHOUSE CREEK 9.0
END DESCRIPTION:
XS GIS Cut Line= 3
      2733561.41     10149920.78      2734035.25       10150310.
      2734680.73     10150428.12
#Sta/Elev= 30
  4386.8 1639.51  4412.9 1639.85  4746.6 1636.26  4754.5 1636.77  4760.9 1635.73
  4796.1 1636.45  4867.8 1635.82  4896.5 1636.58  4938.2 1635.81  4960.4 1636.28
  4981.2 1635.79  4995.6 1634.29  4998.5  1630.5  5001.1  1630.5  5007.9 1630.07
  5008.3 1629.57  5013.4 1630.07    5029 1633.61  5061.4 1635.32  5103.9 1634.54
  5142.8 1635.61  5183.4 1635.48  5193.6  1636.4  5215.4 1635.37  5263.5 1635.84
  5356.3 1634.73  5427.4 1638.76  5478.2 1639.91  5508.7  1641.7  5656.2 1643.29
#Mann= 5 ,-1 , 0
  4386.8     .05       0  5001.1     .12       0  5007.9     .05       0
  5013.4     .12       0    5029     .05       0
Bank Sta=5007.9,5013.4
XS Rating Curve= 0 ,0
Exp/Cntr=0.3,0.1

Type RM Length L Ch R = 1 ,4000    ,500,500,500
BEGIN DESCRIPTION:
BLOCKHOUSE CREEK 8.0
END DESCRIPTION:
XS GIS Cut Line= 3
      2733436.39     10150129.09      2733842.58     10150706.78
      2734230.68     10150778.11
#Sta/Elev= 30
  4293.8 1637.06    4425 1634.95  4454.6 1635.36  4469.4 1634.31  4475.5 1635.01
  4561.8 1632.71  4568.2  1633.2  4654.2 1632.73  4683.8 1631.72  4713.4 1632.43
  4763.2 1630.75  4885.8 1630.22  4963.4 1629.79  4971.1 1628.64  4984.4 1624.79
  4993.1 1623.32  4995.6 1622.02  4996.1 1621.52  5001.1 1622.02  5007.8 1622.39
  5013.3 1624.13  5033.7 1625.75    5054 1626.88  5104.8 1627.65  5125.2 1629.88
  5135.3 1629.32  5145.5 1631.56    5298 1636.26  5336.4    1637  5394.6 1636.48
#Mann= 5 ,-1 , 0
  4293.8     .05       0  4568.2     .12       0  4885.8     .05       0
  4995.6     .05       0  5001.1     .05       0
Bank Sta=4995.6,5001.1
XS Rating Curve= 0 ,0
Exp/Cntr=0.3,0.1

Type RM Length L Ch R = 1 ,3500    ,500,500,500
BEGIN DESCRIPTION:
BLOCKHOUSE CREEK 7.0
END DESCRIPTION:
XS GIS Cut Line= 3
      2733075.29     10150469.38      2733528.43      10151070.9
      2733980.73     10151128.12
#Sta/Elev= 30
  4246.9 1631.36  4342.2 1630.45  4377.6 1629.31  4585.8 1627.06  4721.1 1625.98
  4771.1 1626.09  4785.7 1625.37  4827.5 1625.56  4835.6 1625.02  4906.4 1625.28
  4950.2 1624.22    4971 1622.79  4977.7 1622.07  4989.1 1618.14  4989.5 1617.64
  4994.1 1617.64  4994.6 1618.14  4998.3  1619.8  5017.4 1622.34  5047.6 1623.68
  5135.2 1626.46  5140.3 1626.02  5148.4 1626.87  5259.3    1631  5289.5 1631.59
  5300.6 1632.49  5329.9 1632.81  5339.9 1633.63  5375.7 1634.56  5455.9 1635.66
#Mann= 3 ,-1 , 0
  4246.9     .05       0  4989.1     .05       0  4994.6     .05       0
Bank Sta=4989.1,4994.6
XS Rating Curve= 0 ,0
Exp/Cntr=0.3,0.1

Type RM Length L Ch R = 1 ,3000    ,500,500,500
BEGIN DESCRIPTION:
BLOCKHOUSE CREEK 6.0
END DESCRIPTION:
XS GIS Cut Line= 3
      2732825.32     10150844.41      2733307.32     10151473.86
      2734212.48      10151843.7
#Sta/Elev= 30
  4207.2 1625.06  4270.1 1625.67  4313.7 1623.62  4363.5 1622.77  4477.8 1622.28
    4563 1623.05  4612.8  1621.9  4666.7 1621.69  4691.7 1621.71  4706.3 1620.74
  4741.6  1621.6  4820.4 1620.84  4876.9 1620.72    4912 1620.52    4974 1618.65
  4984.6 1616.91  4988.1 1614.67  4988.6 1614.17  4993.3 1614.17  4993.8 1614.67
  5007.4 1615.85  5012.8 1617.55  5019.8 1618.49  5090.3 1622.57  5191.8 1625.38
  5311.5  1624.9    5459 1625.79  5619.4 1625.79  5916.4 1629.69  5977.8 1629.75
#Mann= 7 ,-1 , 0
  4207.2     .05       0  4666.7     .12       0  4820.4     .05       0
  4876.9     .12       0    4974     .05       0  4988.1     .05       0
  4993.8     .05       0
Bank Sta=4988.1,4993.8
XS Rating Curve= 0 ,0
Exp/Cntr=0.3,0.1

Type RM Length L Ch R = 1 ,2500    ,500,500,500
BEGIN DESCRIPTION:
BLOCKHOUSE CREEK 5.0
END DESCRIPTION:
XS GIS Cut Line= 3
      2732700.32      10151136.1      2733050.61     10151886.58
       2733741.3     10152513.08
#Sta/Elev= 30
  4171.8 1619.15  4212.6 1618.61  4310.5 1619.85  4435.8 1618.46    4647 1618.55
    4904  1617.6  4909.5 1616.27    4941 1615.48  4963.1  1612.9  4972.6 1614.25
  4985.1 1612.43  4997.2 1611.63  4997.6 1611.13  5002.9 1611.63  5007.9 1611.63
  5015.4 1613.97  5029.6 1614.96  5192.4 1618.55  5355.3 1617.69  5362.1 1617.16
  5418.8 1617.66  5425.6 1617.15  5560.4 1617.15  5581.7 1617.68  5602.7  1616.8
  5610.1 1617.43  5616.8 1616.71  5645.2 1616.68  5779.7 1618.07  5932.5 1621.62
#Mann= 3 ,-1 , 0
  4171.8     .05       0  4997.2     .03       0  5002.9     .05       0
Bank Sta=4997.2,5002.9
XS Rating Curve= 0 ,0
Exp/Cntr=0.3,0.1

Type RM Length L Ch R = 1 ,2000    ,500,500,500
BEGIN DESCRIPTION:
BLOCKHOUSE CREEK 4.0
END DESCRIPTION:
XS GIS Cut Line= 4
      2732422.24     10151233.46       2732679.7     10152174.89
      2732702.84     10152248.86      2733390.91     10152693.98
#Sta/Elev= 30
    4024 1617.51  4097.7 1615.53  4220.6 1614.68  4635.3 1613.99    4656 1612.63
  4701.6 1612.61  4770.1 1610.91  4801.2  1610.9  4810.3 1610.07  4956.7 1611.78
    4969 1611.65  4977.4 1609.17  4993.6 1608.79  4994.1 1608.29  4998.9 1608.29
  4999.3 1608.79  5008.6 1610.34  5029.6 1610.72  5068.3  1613.1  5117.8 1613.29
  5256.9 1611.98  5307.2 1612.05  5314.3 1612.67  5335.4  1612.1  5378.6 1612.66
  5414.4 1612.23  5473.9 1613.08  5595.3 1613.21  5791.8 1616.34    5897  1617.3
#Mann= 3 ,-1 , 0
    4024     .05       0  4993.6     .05       0  4999.3     .05       0
Bank Sta=4993.6,4999.3
XS Rating Curve= 0 ,0
Exp/Cntr=0.3,0.1

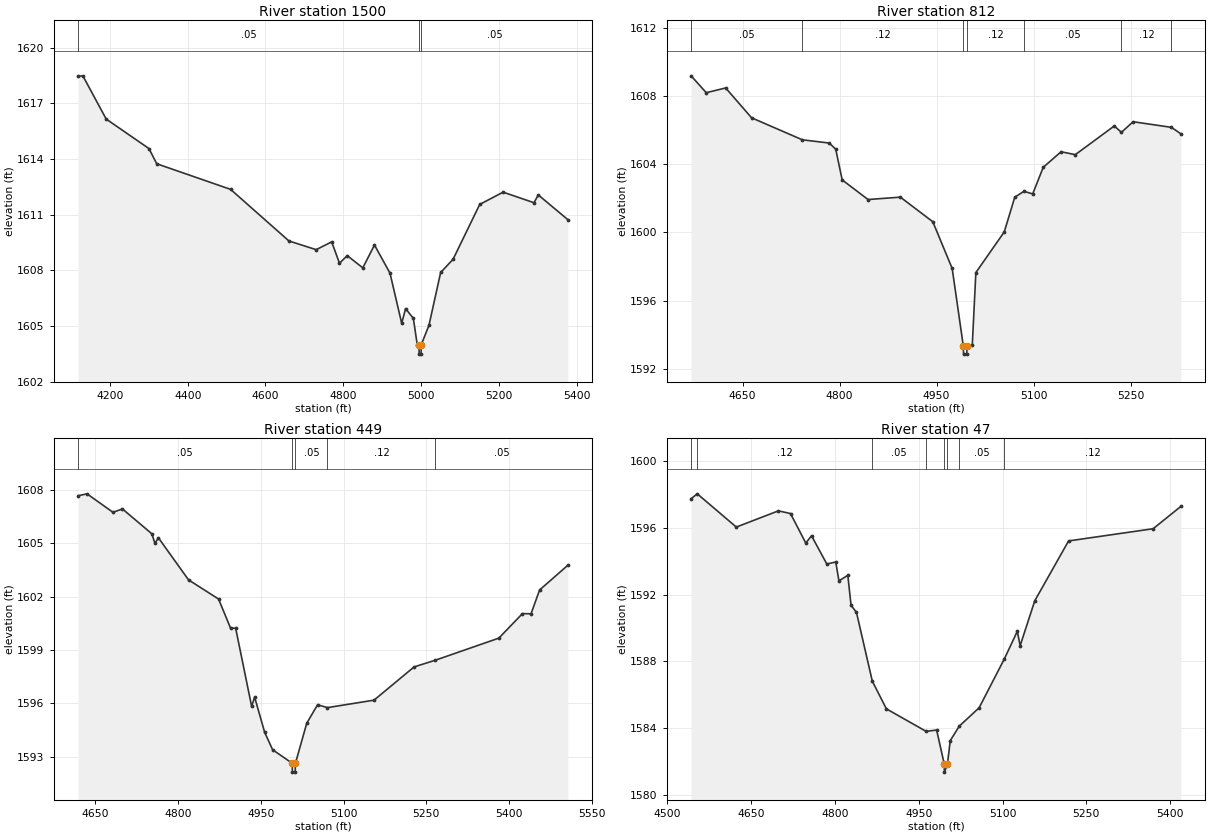
Type RM Length L Ch R = 1 ,1500    ,688,688,688
BEGIN DESCRIPTION:
BLOCKHOUSE CREEK 3.0
END DESCRIPTION:
XS GIS Cut Line= 3
      2732255.86     10151170.74      2732263.34     10152052.81
      2732298.39     10152428.78
#Sta/Elev= 30
  4117.9 1618.46  4130.3 1618.49  4190.3 1616.16  4300.3 1614.57  4320.3 1613.75
  4510.3 1612.37  4660.3 1609.59  4730.3 1609.12  4770.3 1609.54  4790.3 1608.39
  4810.3  1608.8  4850.3 1608.14  4880.3 1609.37  4920.3 1607.85  4950.3 1605.15
  4960.3 1605.94  4980.3 1605.42  4990.3    1604  4994.8 1603.99  4995.3 1603.49
  5000.1 1603.49  5000.5 1603.99  5020.4 1605.04  5050.5 1607.89  5082.4  1608.6
    5151 1611.56  5211.2 1612.22  5290.6 1611.65  5301.6 1612.07  5377.6 1610.74
#Mann= 3 ,-1 , 0
  4117.9     .05       0  4994.8     .05       0  5000.5     .05       0
Bank Sta=4994.8,5000.5
XS Rating Curve= 0 ,0
Exp/Cntr=0.3,0.1

Type RM Length L Ch R = 1 ,812     ,363,363,363
BEGIN DESCRIPTION:
BLOCKHOUSE CREEK 2.0
END DESCRIPTION:
XS GIS Cut Line= 3
      2731632.09     10151589.72       2731615.5       10152019.
      2731769.46      10152308.4
#Sta/Elev= 30
  4570.4 1609.17  4593.8 1608.18  4623.8 1608.46  4663.9 1606.71  4742.4 1605.42
    4784 1605.23    4794 1604.87    4804 1603.07    4844 1601.92    4894 1602.06
  4944.1 1600.62  4974.1 1597.88  4991.2 1593.36  4991.7 1592.86  4996.6 1592.86
    4997 1593.36  5005.2 1593.41  5010.7 1597.64  5054.6 1600.02  5070.9 1602.06
  5085.1  1602.4  5098.6 1602.25  5114.9 1603.81  5142.5 1604.72  5164.5 1604.55
  5224.7 1606.23  5235.8 1605.86  5253.9 1606.48  5313.1 1606.15  5327.8 1605.77
#Mann= 7 ,-1 , 0
  4570.4     .05       0  4742.4     .12       0  4991.2     .07       0
    4997     .12       0  5085.1     .05       0  5235.8     .12       0
  5313.1     .05       0
Bank Sta=4991.2,4997
XS Rating Curve= 0 ,0
Exp/Cntr=0.3,0.1

Type RM Length L Ch R = 1 ,449     ,402,402,402
BEGIN DESCRIPTION:
Mapping XS 3a8b8557
END DESCRIPTION:
XS GIS Cut Line= 4
      2731415.45     10151569.17       2731273.1       10151899.
      2731307.83     10152051.78      2731627.28     10152242.76
#Sta/Elev= 30
  4618.4 1607.68  4634.7 1607.79  4681.8 1606.75  4698.9 1606.94  4752.3 1605.54
  4757.7 1605.01  4764.3 1605.31  4818.7 1602.95  4873.2 1601.87    4895 1600.23
  4904.2 1600.23  4933.2 1595.83  4938.6 1596.35  4956.7 1594.38  4971.2 1593.39
  5006.7 1592.63  5007.2 1592.13  5012.1 1592.13  5012.6 1592.63  5033.1 1594.88
  5052.7 1595.92  5070.7 1595.76  5155.1 1596.18  5227.7 1598.05  5266.5 1598.43
  5381.4 1599.67  5424.2 1601.05  5439.8 1601.04  5455.3 1602.38  5506.5 1603.77
#Mann= 5 ,-1 , 0
  4618.4     .05       0  5006.7     .05       0  5012.6     .05       0
  5070.7     .12       0  5266.5     .05       0
Bank Sta=5006.7,5012.6
XS Rating Curve= 0 ,0
Exp/Cntr=0.3,0.1

Type RM Length L Ch R = 1 ,47      ,0,0,0
BEGIN DESCRIPTION:
BLOCKHOUSE CREEK 1.0
END DESCRIPTION:
XS GIS Cut Line= 4
      2731208.91     10151785.04       2731050.5     10152067.16
      2731049.25       10152201.      2731465.03     10152255.96
#Sta/Elev= 30
  4542.6 1597.74  4553.6 1598.03  4623.5 1596.04  4698.8 1597.01  4720.5 1596.85
  4747.9 1595.08  4758.1 1595.52  4785.5 1593.83  4801.5 1593.95  4807.2 1592.82
  4823.1 1593.15  4828.9 1591.36  4838.6 1590.93  4866.9 1586.82  4892.1 1585.16
  4963.3 1583.81  4982.1 1583.89  4995.6 1581.87  4996.1 1581.37  5001.5 1581.87
  5006.5 1583.26  5022.8 1584.13  5058.1 1585.22  5103.2 1588.14  5126.5  1589.8
  5131.6 1588.94  5157.8 1591.63  5218.3 1595.21  5369.6 1595.94  5419.4 1597.28
#Mann= 8 ,-1 , 0
  4542.6     .05       0  4553.6     .12       0  4866.9     .05       0
  4963.3     .12       0  4995.6     .07       0  5001.5     .12       0
  5022.8     .05       0  5103.2     .12       0
Bank Sta=4995.6,5001.5
XS Rating Curve= 0 ,0
Exp/Cntr=0.3,0.1

Chan Stop Cuts=-1
Use User Specified Reach Order=0
Composite Channel Slope=5