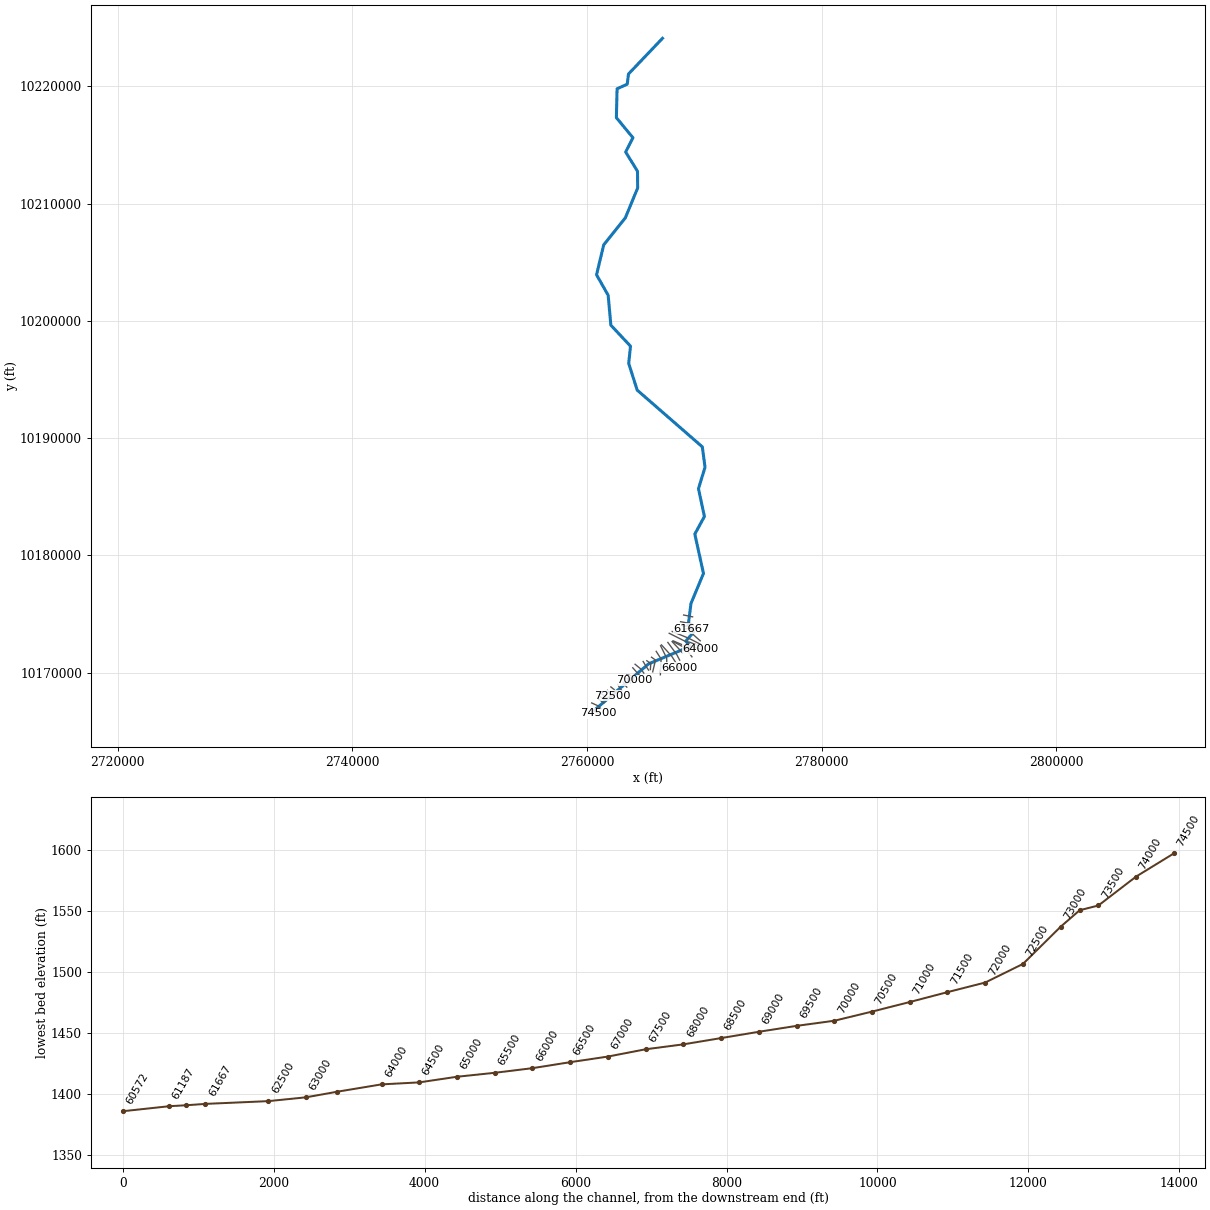
--- BULLHEAD CREEK.prj (project) ---

Proj Title=BULLHEAD CREEK Base Level Engineering
Current Plan=p01
Default Exp/Contr=0.3,0.1
English Units
Geom File=g01
Flow File=f01
Plan File=p01
BEGIN DESCRIPTION:
BULLHEAD CREEK
END DESCRIPTION:

--- BULLHEAD CREEK.p01 (plan) ---

Plan Title=Multiple Run
Short Identifier=Multiple
Geom File=g01
Flow File=f01
Subcritical Flow
K Sum by GR= 0
Std Step Tol= 0.01
Critical Tol= 0.01
Num of Std Step Trials= 20
Max Error Tol= 0.3
Flow Tol Ratio= 0.001
Split Flow NTrial= 30
Split Flow Tol= 0.02
Split Flow Ratio= 0.02
Log Output Level= 0
Friction Slope Method= 1
Unsteady Friction Slope Method= 2
Unsteady Bridges Friction Slope Method= 1
Parabolic Critical Depth
Global Vel Dist=  1 , 1 , 1
Global Log Level= 0
CheckData=True
Encroach Param= -1, 0, 0, 0
BEGIN DESCRIPTION:
Multiple Run
END DESCRIPTION:

--- BULLHEAD CREEK.f01 (steady flow) ---

Flow Title=Multiple
Program Version=4.10
Number of Profiles= 7
Profile Names=10-year,25-year,50-year,1pct_min,100-year,1pct_plu,500-year
River Rch & RM=BULLHEAD CREEK,Reach-1         ,74500
     413     666    1066     832    1448    2523    2035
River Rch & RM=BULLHEAD CREEK,Reach-1         ,64500
     706    1188    1696    1183    2322    4559    3234
River Rch & RM=BULLHEAD CREEK,Reach-1         ,56000
     900    1536    2254    1565    3114    6198    4326
River Rch & RM=BULLHEAD CREEK,Reach-1         ,53500
    1012    1739    2589    1793    3593    7200    4987
River Rch & RM=BULLHEAD CREEK,Reach-1         ,51500
    1264    2205    3270    2227    4565    9358    6315
River Rch & RM=BULLHEAD CREEK,Reach-1         ,47500
    1720    3044    4845    3356    6847   13967    9430
River Rch & RM=BULLHEAD CREEK,Reach-1         ,44500
    2324    4198    6842    4669    9780   20487   13447
River Rch & RM=BULLHEAD CREEK,Reach-1         ,37331
    2385    4320    6942    4699    9920   20943   13629
River Rch & RM=BULLHEAD CREEK,Reach-1         ,35500
    2635    4825    7804    5287   11189   23680   15310
River Rch & RM=BULLHEAD CREEK,Reach-1         ,34000
    3442    6432   10503    7125   15124   32100   20470
River Rch & RM=BULLHEAD CREEK,Reach-1         ,30500
    4966    9387   15280   10340   21987   46756   29357
River Rch & RM=BULLHEAD CREEK,Reach-1         ,27000
    5064    9590   15512   10345   22336   48228   29824
River Rch & RM=BULLHEAD CREEK,Reach-1         ,22000
    5086    9642   15532   10272   22372   48725   29875
River Rch & RM=BULLHEAD CREEK,Reach-1         ,19000
    5269    9992   16077   10617   23149   50476   30872
River Rch & RM=BULLHEAD CREEK,Reach-1         ,18500
    5271   10014   15987   10414   23033   50946   30724
River Rch & RM=BULLHEAD CREEK,Reach-1         ,13000
    5367   10211   16231   10471   23398   52280   31206
River Rch & RM=BULLHEAD CREEK,Reach-1         ,8500
    5617   10723   17062   10826   24656   56151   32948
Boundary for River Rch & Prof#=BULLHEAD CREEK,Reach-1         , 1
Up Type= 0
Dn Type= 3
Dn Slope=0.0005
Boundary for River Rch & Prof#=BULLHEAD CREEK,Reach-1         , 2
Up Type= 0
Dn Type= 3
Dn Slope=0.0005
Boundary for River Rch & Prof#=BULLHEAD CREEK,Reach-1         , 3
Up Type= 0
Dn Type= 3
Dn Slope=0.0005
Boundary for River Rch & Prof#=BULLHEAD CREEK,Reach-1         , 4
Up Type= 0
Dn Type= 3
Dn Slope=0.0005
Boundary for River Rch & Prof#=BULLHEAD CREEK,Reach-1         , 5
Up Type= 0
Dn Type= 3
Dn Slope=0.0005
Boundary for River Rch & Prof#=BULLHEAD CREEK,Reach-1         , 6
Up Type= 0
Dn Type= 3
Dn Slope=0.0005
Boundary for River Rch & Prof#=BULLHEAD CREEK,Reach-1         , 7
Up Type= 0
Dn Type= 3
Dn Slope=0.0005
DSS Import GetInterval= 0
DSS Import GetPeak= 0
DSS Import FillOption= 0

--- BULLHEAD CREEK.g01 (geometry) ---

Geom Title=Existing Conditions

River Reach=BULLHEAD CREEK,Reach-1
Reach XY= 30
      2760552.25     10166714.00      2765253.25     10170734.00
      2768808.50     10172227.00      2768429.25     10172683.00
      2769111.50     10173453.00      2768639.00     10174064.00
      2768871.25     10175897.00      2769935.50     10178446.00
      2769196.00     10181805.00      2770013.75     10183305.00
      2769508.00     10185676.00      2770067.25     10187510.00
      2769834.00     10189247.00      2764287.00     10194082.00
      2763560.25     10196362.00      2763715.25     10197834.00
      2762040.75     10199623.00      2761811.00     10202173.00
      2760821.50     10203919.00      2761431.75     10206471.00
      2763273.50     10208775.00      2764323.50     10211319.00
      2764313.25     10212746.00      2763302.75     10214394.00
      2763923.50     10215610.00      2762511.00     10217319.00
      2762571.50     10219787.00      2763434.00     10220177.00
      2763546.50     10221050.00      2766440.25     10224087.00

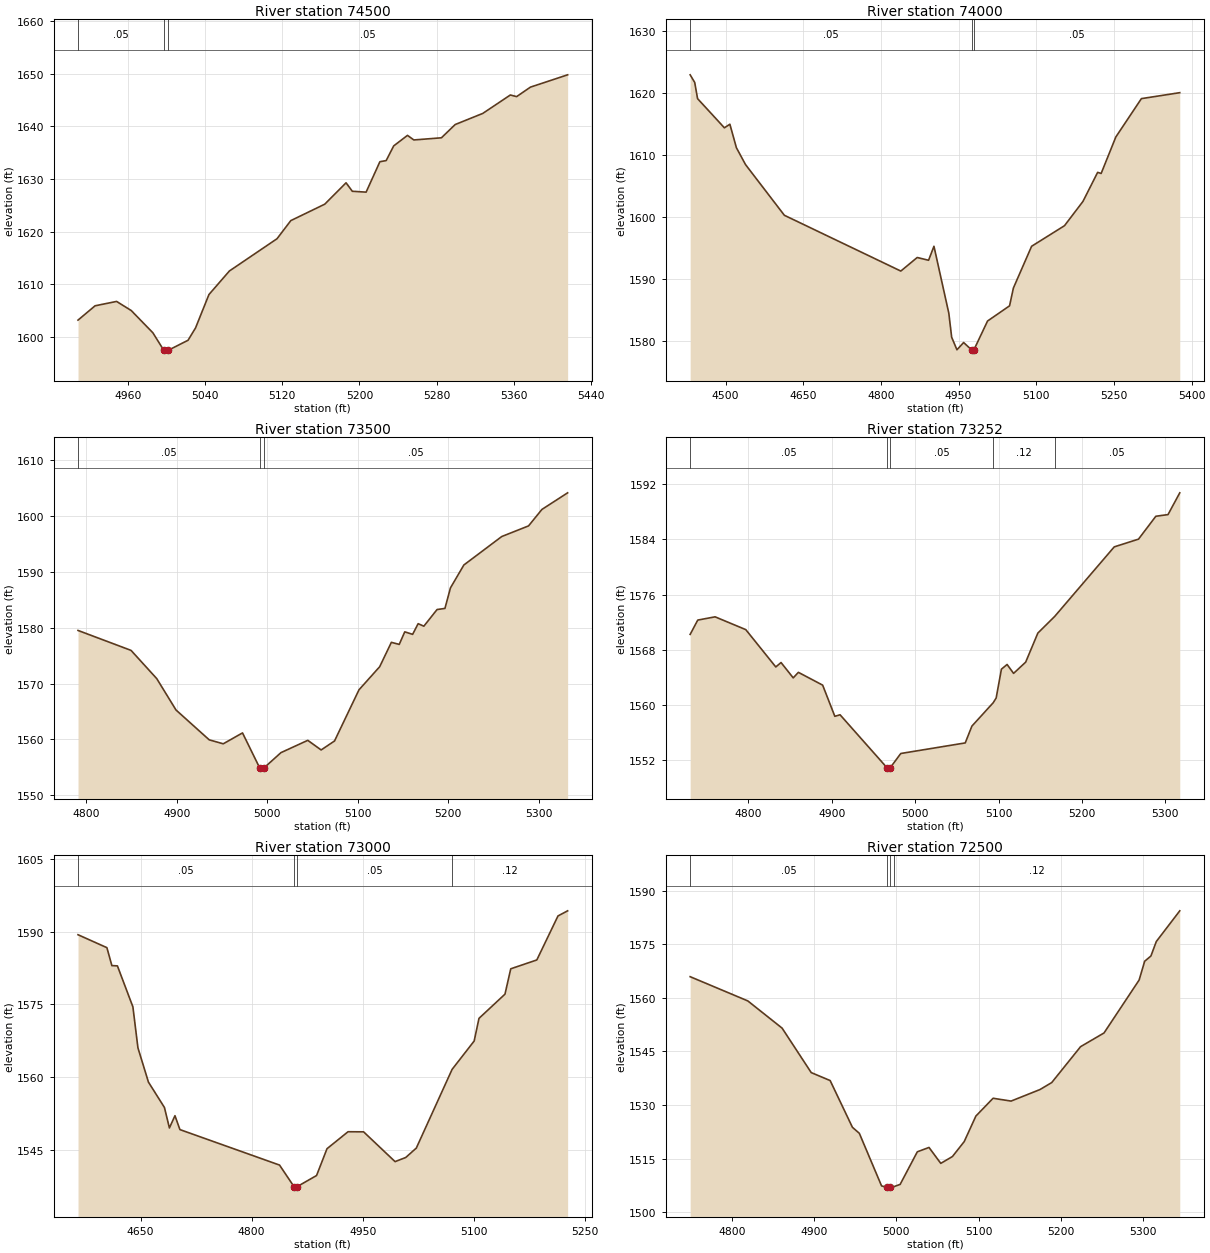
Type RM Length L Ch R = 1,74500,500,500,500
BEGIN DESCRIPTION:
BULLHEAD CREEK 149.0
END DESCRIPTION:
XS GIS Cut Line= 3
      2760529.88     10166822.15      2760612.04     10166780.96
      2760930.79     10166513.81
#Sta/Elev= 30
  4908.1 1603.19  4925.8 1605.91  4948.1 1606.74  4963.3 1605.01  4985.7 1600.79
  4997.2 1597.42  4997.5 1596.92  5001.2 1597.42  5022.2 1599.36  5030.0 1601.71
  5043.9 1608.05  5065.1 1612.52  5114.5 1618.65  5128.8 1622.09  5164.0 1625.21
  5186.1 1629.27  5192.6 1627.66  5206.9 1627.50  5221.2 1633.28  5227.7 1633.49
  5235.5 1636.28  5249.8 1638.28  5256.4 1637.41  5285.0 1637.82  5299.3 1640.34
  5327.9 1642.45  5356.5 1645.95  5363.0 1645.64  5377.3 1647.44  5415.9 1649.78
#Mann=3,-1,0
  4908.1    0.05       0  4997.2    0.05       0  5001.2    0.05       0
Bank Sta=4997.2,5001.2
Exp/Cntr=0.3,0.1

Type RM Length L Ch R = 1,74000,500,500,500
BEGIN DESCRIPTION:
BULLHEAD CREEK 148.0
END DESCRIPTION:
XS GIS Cut Line= 3
      2760405.71     10167403.10      2760924.19     10167170.16
      2761200.01     10166913.01
#Sta/Elev= 30
  4431.6 1622.90  4440.4 1621.67  4445.9 1619.06  4497.7 1614.35  4508.3 1614.93
  4520.9 1611.14  4538.5 1608.42  4613.5 1600.24  4838.4 1591.24  4870.1 1593.43
  4892.0 1592.98  4902.4 1595.24  4931.1 1584.44  4936.6 1580.56  4946.8 1578.54
  4959.7 1579.71  4975.4 1578.50  4975.7 1578.00  4979.4 1578.50  5005.9 1583.18
  5048.4 1585.63  5055.8 1588.50  5091.0 1595.24  5154.5 1598.56  5190.1 1602.47
  5218.5 1607.16  5225.3 1606.99  5253.6 1612.87  5303.0 1619.06  5377.1 1620.02
#Mann=3,-1,0
  4431.6    0.05       0  4975.4    0.05       0  4979.4    0.05       0
Bank Sta=4975.4,4979.4
Exp/Cntr=0.3,0.1

Type RM Length L Ch R = 1,73500,248,248,248
BEGIN DESCRIPTION:
BULLHEAD CREEK 147.0
END DESCRIPTION:
XS GIS Cut Line= 3
      2761005.70     10167703.10      2761184.04     10167593.74
      2761455.72     10167403.09
#Sta/Elev= 30
  4790.8 1579.51  4849.4 1575.94  4877.8 1570.89  4899.1 1565.27  4935.8 1559.93
  4951.3 1559.22  4972.6 1561.17  4991.8 1554.83  4992.1 1554.33  4995.8 1554.83
  5015.1 1557.64  5044.7 1559.84  5059.5 1558.12  5074.3 1559.73  5101.3 1568.88
  5124.2 1573.02  5137.1 1577.38  5145.8 1577.01  5151.9 1579.26  5160.6 1578.81
  5166.7 1580.72  5173.0 1580.27  5187.6 1583.25  5196.3 1583.45  5202.4 1587.12
  5217.2 1591.22  5259.1 1596.32  5288.7 1598.22  5303.5 1601.17  5331.9 1604.14
#Mann=3,-1,0
  4790.8    0.05       0  4991.8    0.03       0  4995.8    0.05       0
Bank Sta=4991.8,4995.8
Exp/Cntr=0.3,0.1

Type RM Length L Ch R = 1,73252,252,252,252
BEGIN DESCRIPTION:
Mapping XS fb131495
END DESCRIPTION:
XS GIS Cut Line= 2
      2761142.44     10167932.86      2761610.95     10167578.87
#Sta/Elev= 30
  4730.2 1570.24  4739.3 1572.31  4760.1 1572.78  4796.9 1570.93  4832.9 1565.53
  4839.2 1566.17  4853.8 1563.95  4860.0 1564.75  4889.1 1562.90  4903.7 1558.39
  4910.0 1558.61  4966.2 1550.96  4966.5 1550.46  4970.2 1550.96  4982.8 1553.01
  5060.1 1554.54  5068.1 1556.97  5093.7 1560.36  5097.2 1561.04  5103.5 1565.21
  5110.3 1565.89  5118.1 1564.60  5132.6 1566.23  5147.2 1570.43  5167.4 1572.84
  5238.8 1582.90  5267.9 1584.02  5288.7 1587.33  5303.3 1587.57  5317.4 1590.72
#Mann=5,-1,0
  4730.2    0.05       0  4966.2    0.05       0  4970.2    0.05       0
  5093.7    0.12       0  5167.4    0.05       0
Bank Sta=4966.2,4970.2
Exp/Cntr=0.3,0.1

Type RM Length L Ch R = 1,73000,500,500,500
BEGIN DESCRIPTION:
BULLHEAD CREEK 146.0
END DESCRIPTION:
XS GIS Cut Line= 3
      2761226.03     10168228.14      2761547.00     10167935.43
      2761720.76     10167789.83
#Sta/Elev= 30
  4565.6 1589.35  4604.6 1586.69  4611.3 1583.00  4618.8 1582.94  4639.7 1574.51
  4646.5 1566.08  4660.7 1559.02  4682.3 1553.80  4689.0 1549.59  4696.5 1552.11
  4703.2 1549.25  4837.7 1541.95  4857.3 1537.50  4857.5 1537.00  4861.3 1537.50
  4887.7 1539.80  4901.8 1545.32  4930.2 1548.81  4951.2 1548.79  4993.7 1542.66
  5008.1 1543.51  5022.4 1545.45  5070.7 1561.64  5100.5 1567.48  5107.0 1572.14
  5142.1 1577.12  5149.9 1582.34  5185.1 1584.16  5213.7 1593.22  5226.7 1594.27
#Mann=4,-1,0
  4565.6    0.05       0  4857.3    0.05       0  4861.3    0.05       0
  5070.7    0.12       0
Bank Sta=4857.3,4861.3
Exp/Cntr=0.3,0.1

Type RM Length L Ch R = 1,72500,500,500,500
BEGIN DESCRIPTION:
BULLHEAD CREEK 145.0
END DESCRIPTION:
XS GIS Cut Line= 3
      2761755.55     10168479.87      2761905.07     10168278.77
      2762130.76     10168018.22
#Sta/Elev= 30
  4749.4 1565.91  4819.5 1559.14  4861.2 1551.53  4896.6 1539.10  4919.6 1536.88
  4946.7 1523.81  4955.1 1522.13  4982.1 1507.44  4988.5 1507.03  4988.8 1506.53
  4992.5 1507.03  4996.8 1507.20  5004.7 1507.85  5025.6 1516.96  5039.8 1518.18
  5054.1 1513.73  5068.3 1515.64  5082.6 1519.81  5096.8 1526.95  5117.7 1531.93
  5139.6 1531.14  5174.7 1534.36  5189.0 1536.31  5224.1 1546.35  5252.6 1550.18
  5295.3 1564.98  5302.0 1570.22  5309.6 1571.69  5316.2 1575.75  5344.7 1584.32
#Mann=4,-1,0
  4749.4    0.05       0  4988.5    0.07       0  4992.5    0.05       0
  4996.8    0.12       0
Bank Sta=4988.5,4992.5
Exp/Cntr=0.3,0.1

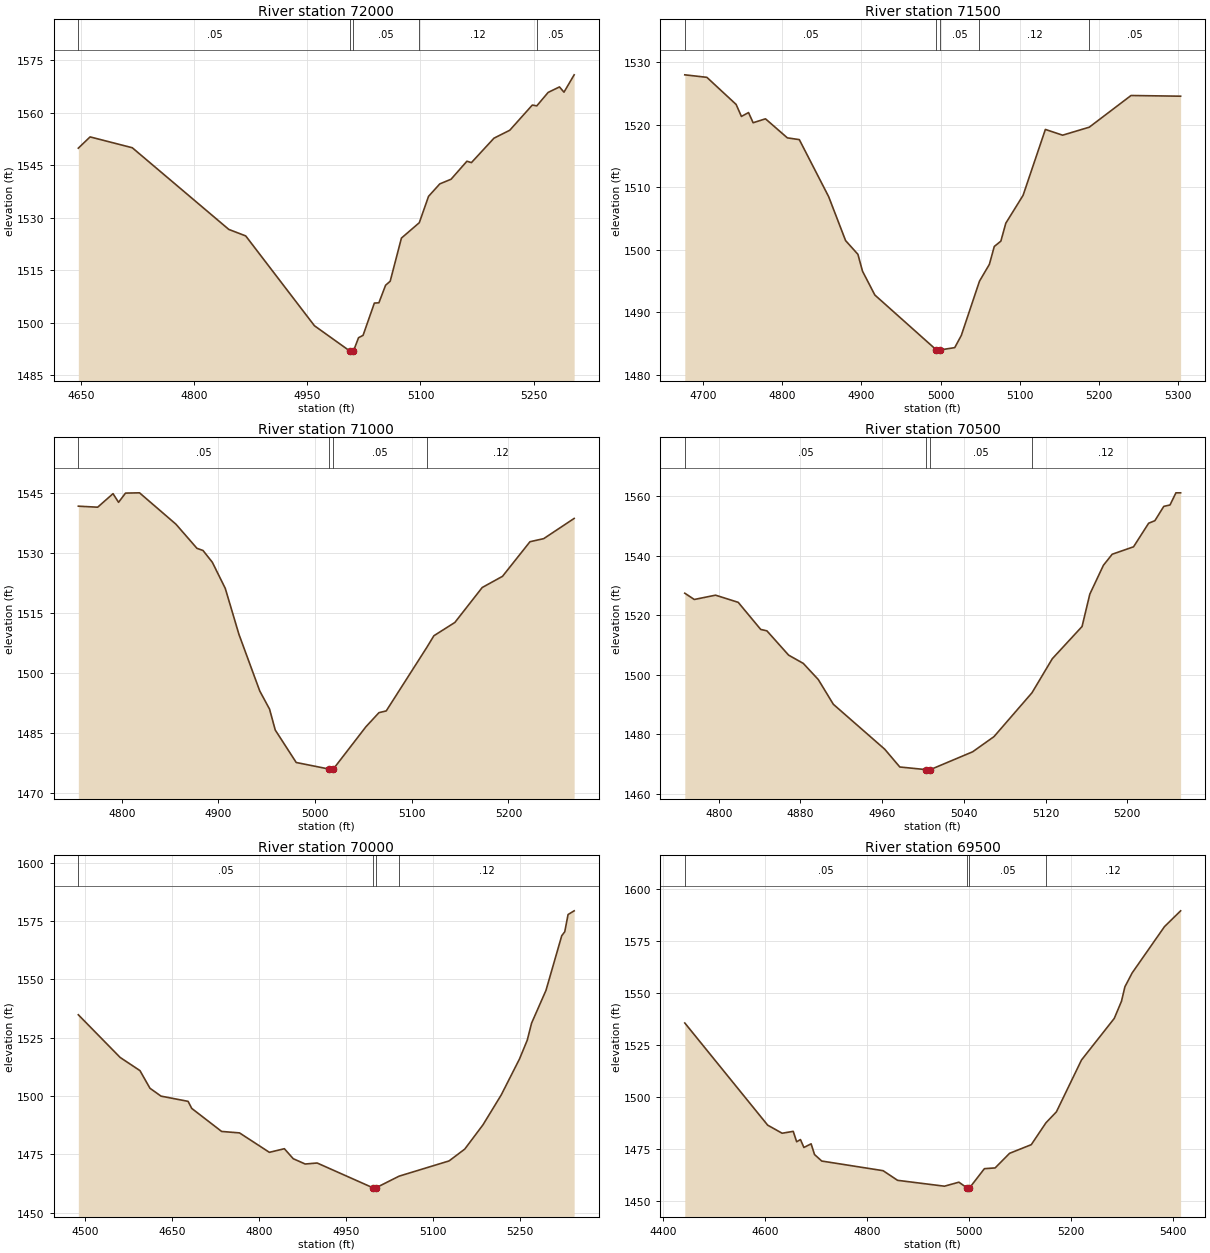
Type RM Length L Ch R = 1,72000,500,500,500
BEGIN DESCRIPTION:
BULLHEAD CREEK 144.0
END DESCRIPTION:
XS GIS Cut Line= 3
      2762042.03     10168770.65      2762318.46     10168549.51
      2762488.86     10168297.87
#Sta/Elev= 30
  4646.0 1549.93  4661.6 1553.15  4717.6 1550.05  4845.7 1526.69  4868.1 1524.84
  4959.3 1499.15  5006.9 1491.82  5007.1 1491.32  5010.9 1491.82  5017.8 1495.73
  5023.8 1496.40  5038.8 1505.63  5044.8 1505.71  5053.7 1510.73  5059.8 1511.88
  5074.7 1524.21  5098.4 1528.61  5110.7 1536.15  5125.6 1539.71  5140.6 1541.05
  5161.6 1546.19  5167.6 1545.80  5197.5 1552.78  5218.5 1555.06  5248.4 1562.26
  5254.3 1562.02  5269.4 1565.87  5284.4 1567.44  5290.4 1565.94  5303.9 1570.90
#Mann=5,-1,0
  4646.0    0.05       0  5006.9    0.05       0  5010.9    0.05       0
  5098.4    0.12       0  5254.3    0.05       0
Bank Sta=5006.9,5010.9
Exp/Cntr=0.3,0.1

Type RM Length L Ch R = 1,71500,500,500,500
BEGIN DESCRIPTION:
BULLHEAD CREEK 143.0
END DESCRIPTION:
XS GIS Cut Line= 3
      2762627.95     10168974.65      2762792.97     10168696.64
      2762975.19     10168453.80
#Sta/Elev= 30
  4676.7 1528.01  4704.6 1527.61  4741.6 1523.27  4748.3 1521.35  4757.3 1521.97
  4763.1 1520.34  4778.7 1520.97  4806.4 1517.92  4821.5 1517.64  4858.6 1508.51
  4880.0 1501.48  4895.6 1499.28  4901.4 1496.58  4917.0 1492.77  4994.9 1483.97
  4995.2 1483.47  4998.9 1483.97  5018.0 1484.35  5026.3 1486.30  5049.3 1494.99
  5061.8 1497.68  5068.0 1500.54  5076.3 1501.39  5082.6 1504.27  5104.4 1508.72
  5132.6 1519.27  5154.4 1518.35  5188.1 1519.63  5240.9 1524.70  5303.6 1524.59
#Mann=5,-1,0
  4676.7    0.05       0  4994.9    0.05       0  4998.9    0.05       0
  5049.3    0.12       0  5188.1    0.05       0
Bank Sta=4994.9,4998.9
Exp/Cntr=0.3,0.1

Type RM Length L Ch R = 1,71000,500,500,500
BEGIN DESCRIPTION:
BULLHEAD CREEK 142.0
END DESCRIPTION:
XS GIS Cut Line= 3
      2763101.01     10169165.67      2763220.74     10168952.03
      2763400.53     10168753.29
#Sta/Elev= 30
  4755.1 1541.70  4775.1 1541.44  4791.0 1544.83  4796.7 1542.66  4803.9 1544.97
  4818.4 1545.04  4856.1 1537.18  4877.8 1531.15  4884.1 1530.60  4893.7 1527.66
  4907.1 1521.12  4921.2 1509.64  4942.8 1495.42  4952.9 1490.90  4958.8 1485.66
  4980.5 1477.53  5014.8 1475.87  5015.0 1475.37  5018.8 1475.87  5052.5 1486.45
  5066.1 1490.01  5073.6 1490.44  5115.8 1506.43  5122.9 1509.26  5144.6 1512.59
  5172.9 1521.34  5193.9 1524.14  5222.3 1532.80  5236.5 1533.57  5268.0 1538.63
#Mann=4,-1,0
  4755.1    0.05       0  5014.8    0.05       0  5018.8    0.05       0
  5115.8    0.12       0
Bank Sta=5014.8,5018.8
Exp/Cntr=0.3,0.1

Type RM Length L Ch R = 1,70500,500,500,500
BEGIN DESCRIPTION:
BULLHEAD CREEK 141.0
END DESCRIPTION:
XS GIS Cut Line= 3
      2763435.21     10169495.54      2763571.66     10169306.43
      2763717.34     10169100.55
#Sta/Elev= 30
  4766.8 1527.36  4776.1 1525.25  4796.9 1526.70  4819.1 1524.29  4841.1 1515.19
  4847.2 1514.70  4868.4 1506.55  4882.8 1503.76  4897.5 1498.33  4912.2 1490.02
  4962.5 1474.92  4977.3 1468.93  5003.1 1468.04  5003.3 1467.54  5007.1 1468.04
  5048.6 1474.04  5069.5 1479.14  5106.7 1493.89  5126.6 1505.34  5155.7 1516.16
  5163.3 1527.04  5176.6 1536.74  5185.2 1540.46  5206.1 1542.96  5220.9 1550.89
  5227.0 1551.74  5235.7 1556.55  5241.8 1557.02  5247.6 1561.11  5252.2 1561.11
#Mann=4,-1,0
  4766.8    0.05       0  5003.1    0.05       0  5007.1    0.05       0
  5106.7    0.12       0
Bank Sta=5003.1,5007.1
Exp/Cntr=0.3,0.1

Type RM Length L Ch R = 1,70000,500,500,500
BEGIN DESCRIPTION:
BULLHEAD CREEK 140.0
END DESCRIPTION:
XS GIS Cut Line= 3
      2763405.73     10169803.10      2763902.56     10169680.68
      2764005.68     10169353.12
#Sta/Elev= 30
  4488.3 1534.83  4560.4 1516.54  4594.6 1510.88  4611.8 1503.33  4630.9 1499.94
  4677.6 1497.70  4683.9 1494.68  4735.4 1484.80  4766.3 1484.17  4817.8 1475.84
  4843.6 1477.39  4859.0 1473.09  4879.6 1470.83  4900.2 1471.26  4997.0 1460.56
  4997.3 1460.06  5001.0 1460.56  5041.6 1465.63  5127.7 1472.16  5154.7 1477.22
  5186.2 1487.65  5217.6 1500.44  5249.1 1515.86  5262.5 1523.92  5270.0 1531.26
  5294.8 1545.29  5322.0 1568.73  5327.2 1570.44  5332.9 1577.82  5343.4 1579.41
#Mann=4,-1,0
  4488.3    0.05       0  4997.0    0.05       0  5001.0    0.05       0
  5041.6    0.12       0
Bank Sta=4997,5001
Exp/Cntr=0.3,0.1

Type RM Length L Ch R = 1,69500,500,500,500
BEGIN DESCRIPTION:
BULLHEAD CREEK 139.0
END DESCRIPTION:
XS GIS Cut Line= 3
      2763905.65     10170403.15      2764276.47     10169986.19
      2764554.91     10169677.92
#Sta/Elev= 30
  4442.0 1535.69  4604.7 1486.61  4633.1 1482.73  4654.9 1483.63  4661.6 1478.63
  4669.1 1479.69  4675.8 1475.89  4690.0 1477.64  4696.7 1472.49  4710.9 1469.37
  4831.3 1464.74  4859.7 1460.11  4951.7 1457.29  4980.1 1459.21  4996.7 1456.38
  4997.0 1455.88  5000.7 1456.38  5030.2 1465.71  5051.2 1466.06  5079.6 1473.08
  5122.2 1477.24  5151.0 1487.74  5171.5 1492.99  5220.8 1517.91  5285.1 1537.88
  5299.3 1546.13  5306.0 1553.06  5320.2 1559.72  5383.7 1581.97  5415.4 1589.57
#Mann=4,-1,0
  4442.0    0.05       0  4996.7    0.05       0  5000.7    0.05       0
  5151.0    0.12       0
Bank Sta=4996.7,5000.7
Exp/Cntr=0.3,0.1

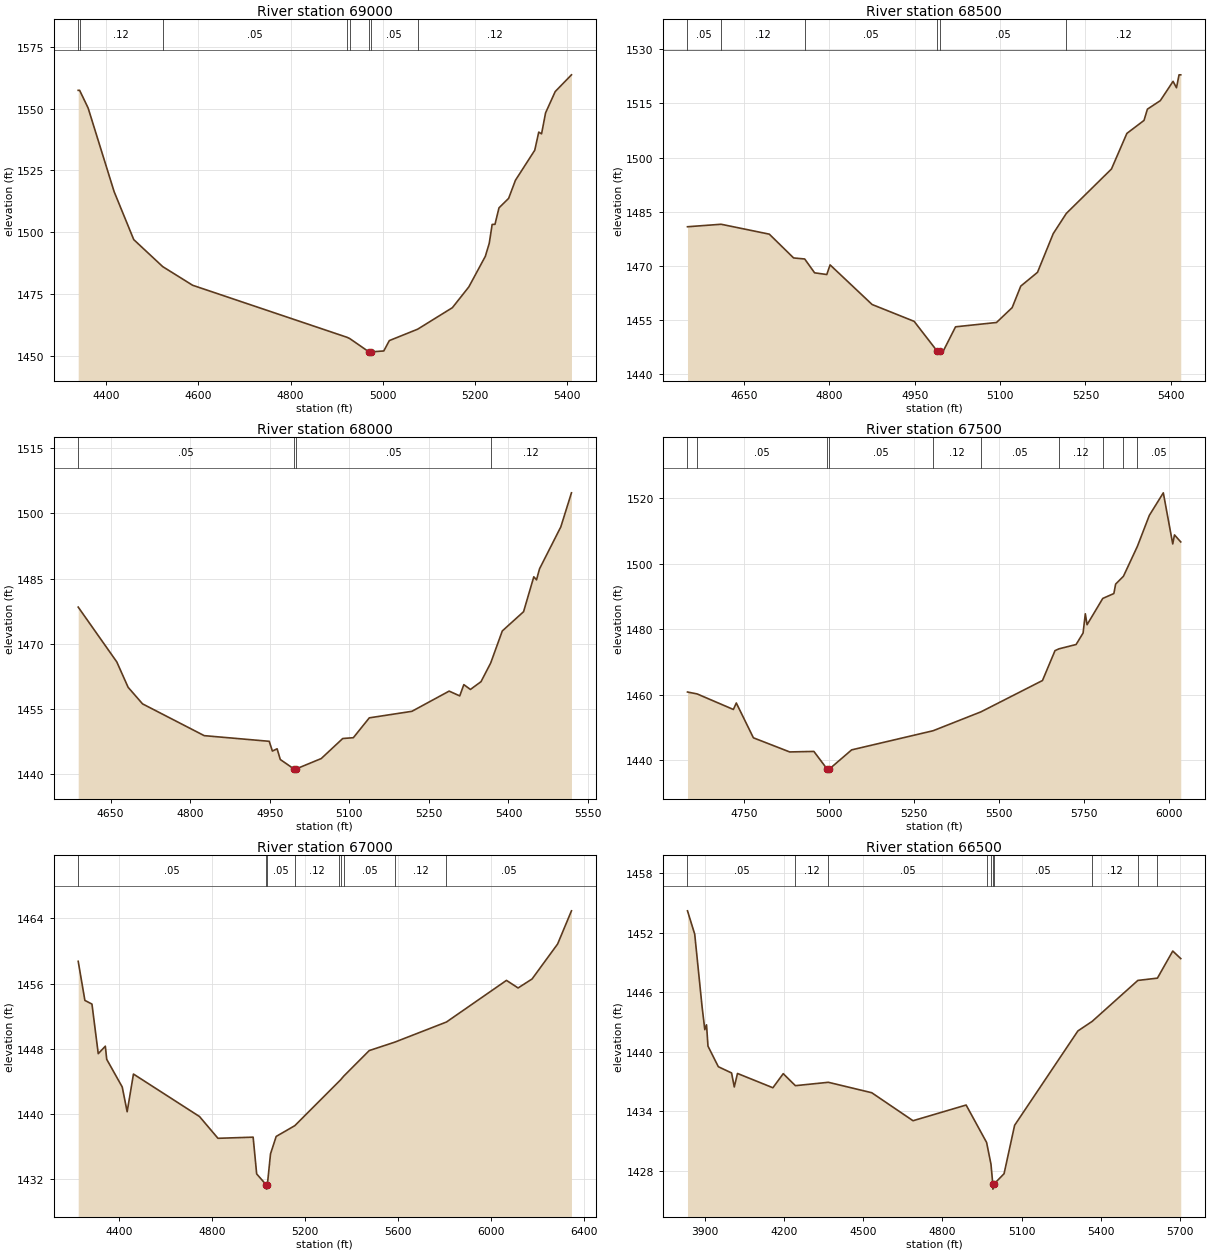
Type RM Length L Ch R = 1,69000,500,500,500
BEGIN DESCRIPTION:
BULLHEAD CREEK 138.0
END DESCRIPTION:
XS GIS Cut Line= 3
      2764105.69     10170703.11      2764613.89     10170281.69
      2764849.72     10169947.52
#Sta/Elev= 30
  4339.8 1557.43  4342.9 1557.43  4361.3 1550.28  4417.7 1516.40  4460.2 1497.00
  4523.0 1486.06  4587.9 1478.51  4922.2 1457.47  4928.3 1456.95  4970.1 1451.54
  4970.3 1451.04  4974.1 1451.54  5002.2 1451.92  5014.2 1456.11  5075.7 1460.74
  5150.9 1469.44  5186.6 1477.87  5222.3 1490.23  5230.8 1495.50  5237.1 1503.14
  5243.2 1503.18  5251.9 1509.85  5272.8 1513.69  5287.6 1521.03  5329.4 1533.17
  5338.1 1540.52  5344.2 1539.82  5352.9 1548.31  5373.8 1556.94  5409.0 1563.71
#Mann=8,-1,0
  4339.8    0.05       0  4342.9    0.12       0  4523.0    0.05       0
  4922.2    0.12       0  4928.3    0.05       0  4970.1    0.05       0
  4974.1    0.05       0  5075.7    0.12       0
Bank Sta=4970.1,4974.1
Exp/Cntr=0.3,0.1

Type RM Length L Ch R = 1,68500,500,500,500
BEGIN DESCRIPTION:
BULLHEAD CREEK 137.0
END DESCRIPTION:
XS GIS Cut Line= 3
      2764793.73     10170936.48      2765025.12     10170551.23
      2765255.66     10170203.15
#Sta/Elev= 30
  4550.6 1480.86  4609.7 1481.55  4694.4 1478.81  4737.1 1472.23  4756.6 1471.94
  4774.0 1468.11  4795.4 1467.64  4801.2 1470.31  4875.1 1459.34  4948.9 1454.69
  4989.7 1446.39  4989.9 1445.89  4993.7 1446.39  5000.0 1446.42  5021.7 1453.17
  5093.7 1454.37  5121.2 1458.48  5136.3 1464.43  5165.7 1468.24  5193.4 1478.96
  5216.4 1484.55  5295.7 1496.84  5322.8 1506.69  5352.9 1510.28  5358.9 1513.40
  5381.6 1515.76  5404.0 1521.10  5410.0 1519.32  5414.5 1522.90  5417.5 1522.90
#Mann=6,-1,0
  4550.6    0.05       0  4609.7    0.12       0  4756.6    0.05       0
  4989.7    0.05       0  4993.7    0.05       0  5216.4    0.12       0
Bank Sta=4989.7,4993.7
Exp/Cntr=0.3,0.1

Type RM Length L Ch R = 1,68000,500,500,500
BEGIN DESCRIPTION:
BULLHEAD CREEK 136.0
END DESCRIPTION:
XS GIS Cut Line= 3
      2765105.65     10171003.13      2765444.57     10170770.45
      2765405.68     10170253.11
#Sta/Elev= 30
  4588.9 1478.44  4661.7 1465.84  4683.0 1460.02  4710.2 1456.21  4826.5 1448.91
  4949.0 1447.61  4955.0 1445.37  4963.9 1445.89  4969.9 1443.43  4995.6 1441.26
  4995.9 1440.76  4999.6 1441.26  5047.1 1443.65  5087.6 1448.25  5107.6 1448.44
  5137.7 1453.00  5218.0 1454.50  5288.2 1459.14  5308.2 1458.04  5315.9 1460.63
  5328.3 1459.52  5348.3 1461.31  5366.6 1465.62  5388.4 1472.96  5428.5 1477.38
  5447.8 1485.40  5452.9 1484.70  5458.6 1487.23  5498.7 1496.86  5518.8 1504.69
#Mann=4,-1,0
  4588.9    0.05       0  4995.6    0.05       0  4999.6    0.05       0
  5366.6    0.12       0
Bank Sta=4995.6,4999.6
Exp/Cntr=0.3,0.1

Type RM Length L Ch R = 1,67500,500,500,500
BEGIN DESCRIPTION:
BULLHEAD CREEK 135.0
END DESCRIPTION:
XS GIS Cut Line= 3
      2765505.67     10171303.12      2765846.30     10171060.86
      2765605.68     10170053.09
#Sta/Elev= 30
  4582.0 1460.85  4610.4 1460.27  4717.3 1455.53  4725.9 1457.51  4776.3 1446.89
  4883.3 1442.58  4954.6 1442.74  4994.6 1437.23  4994.8 1436.73  4998.6 1437.23
  5065.9 1443.21  5306.2 1449.05  5447.4 1454.82  5628.5 1464.36  5665.4 1473.47
  5677.1 1474.02  5727.6 1475.34  5748.2 1478.85  5754.8 1484.71  5759.9 1481.37
  5806.2 1489.39  5838.9 1490.88  5844.1 1493.75  5867.1 1496.14  5908.3 1505.28
  5943.5 1514.72  5984.7 1521.59  6012.5 1506.00  6017.6 1508.76  6036.1 1506.62
#Mann=10,-1,0
  4582.0    0.12       0  4610.4    0.05       0  4994.6    0.05       0
  4998.6    0.05       0  5306.2    0.12       0  5447.4    0.05       0
  5677.1    0.12       0  5806.2    0.05       0  5867.1    0.12       0
  5908.3    0.05       0
Bank Sta=4994.6,4998.6
Exp/Cntr=0.3,0.1

Type RM Length L Ch R = 1,67000,500,500,500
BEGIN DESCRIPTION:
BULLHEAD CREEK 134.0
END DESCRIPTION:
XS GIS Cut Line= 3
      2765905.66     10171803.15      2766323.13     10171149.72
      2766260.75     10169803.67
#Sta/Elev= 30
  4224.6 1458.74  4253.4 1453.94  4283.8 1453.49  4310.9 1447.40  4341.4 1448.32
  4347.3 1446.71  4414.1 1443.31  4435.3 1440.27  4462.4 1444.90  4746.8 1439.68
  4826.1 1437.01  4977.5 1437.15  4992.7 1432.64  5034.6 1431.27  5034.9 1430.77
  5038.6 1431.27  5052.3 1435.10  5076.7 1437.24  5156.8 1438.56  5345.4 1443.95
  5353.9 1444.19  5367.6 1444.65  5477.1 1447.78  5587.4 1448.82  5809.6 1451.29
  6067.8 1456.40  6117.8 1455.47  6177.9 1456.57  6288.0 1460.87  6347.5 1464.94
#Mann=9,-1,0
  4224.6    0.05       0  5034.6    0.05       0  5038.6    0.05       0
  5156.8    0.12       0  5345.4    0.05       0  5353.9    0.12       0
  5367.6    0.05       0  5587.4    0.12       0  5809.6    0.05       0
Bank Sta=5034.6,5038.6
Exp/Cntr=0.3,0.1

Type RM Length L Ch R = 1,66500,500,500,500
BEGIN DESCRIPTION:
BULLHEAD CREEK 133.0
END DESCRIPTION:
XS GIS Cut Line= 3
      2766278.11     10172281.96      2766798.50     10171236.85
      2766811.97     10170532.78
#Sta/Elev= 30
  3832.5 1454.20  3859.9 1451.85  3887.9 1444.53  3898.2 1442.23  3904.7 1442.72
  3910.3 1440.57  3949.5 1438.50  3999.8 1437.87  4010.0 1436.46  4022.2 1437.82
  4156.6 1436.38  4195.8 1437.80  4241.9 1436.59  4367.0 1436.93  4531.6 1435.88
  4688.3 1433.06  4889.8 1434.64  4967.5 1430.87  4984.1 1428.68  4991.0 1426.67
  4991.3 1426.17  4995.0 1426.67  5033.7 1427.72  5073.8 1432.60  5313.8 1442.10
  5368.3 1443.07  5541.4 1447.19  5615.6 1447.42  5673.9 1450.15  5704.2 1449.39
#Mann=10,-1,0
  3832.5    0.05       0  4241.9    0.12       0  4367.0    0.05       0
  4967.5    0.12       0  4984.1    0.05       0  4991.0    0.05       0
  4995.0    0.05       0  5368.3    0.12       0  5541.4    0.05       0
  5615.6    0.12       0
Bank Sta=4991,4995
Exp/Cntr=0.3,0.1

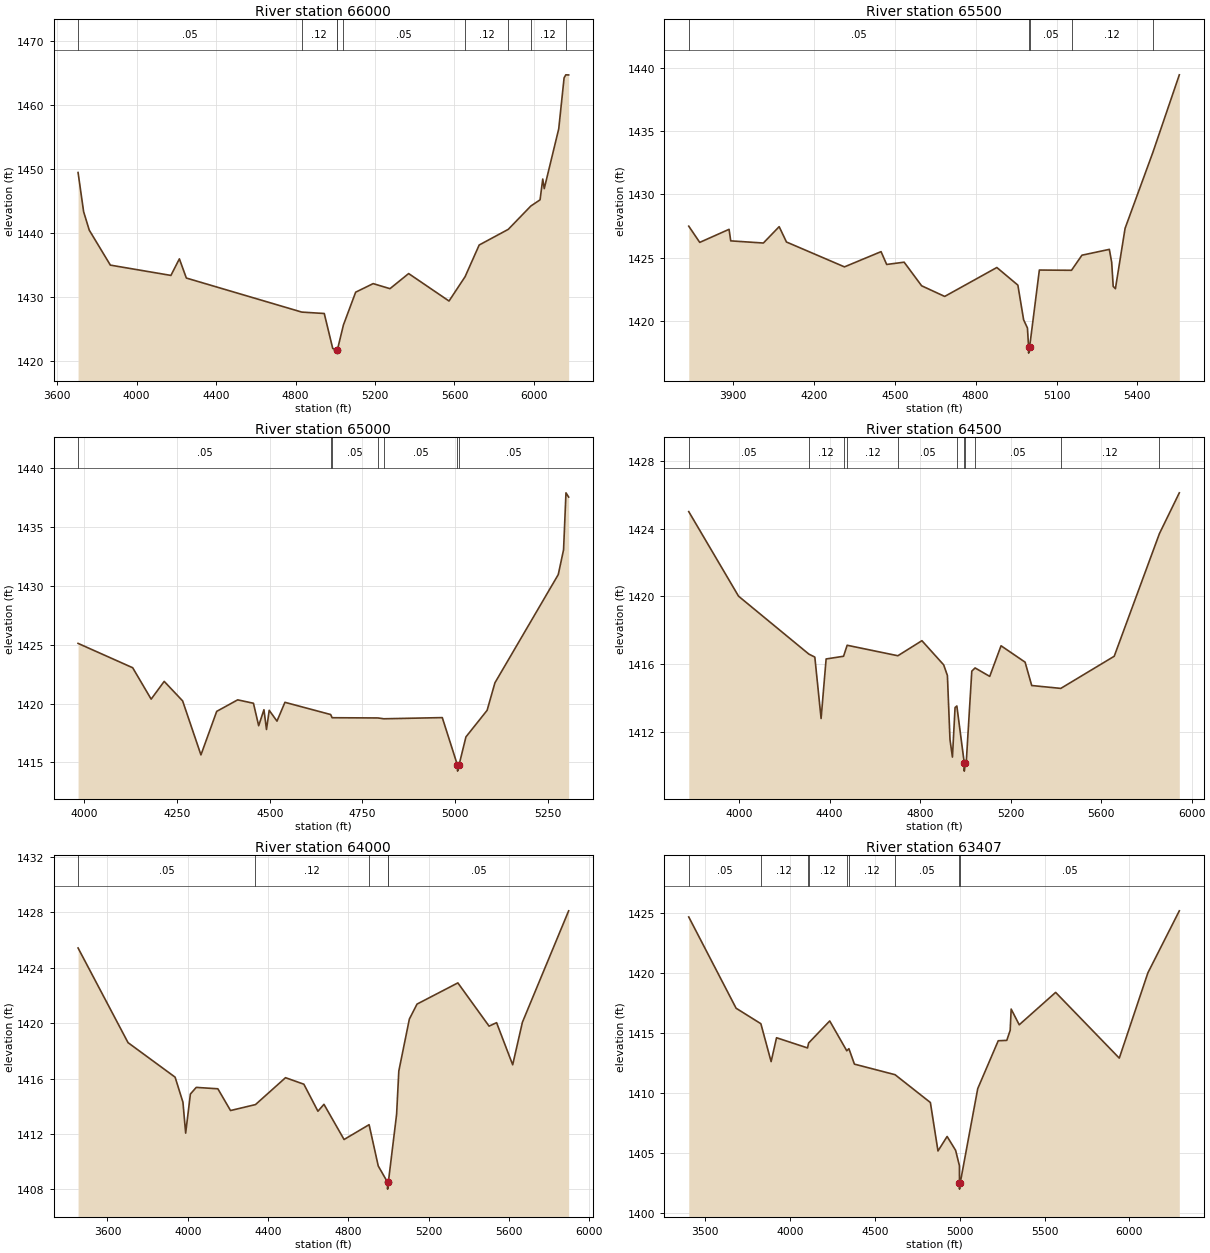
Type RM Length L Ch R = 1,66000,500,500,500
BEGIN DESCRIPTION:
BULLHEAD CREEK 132.0
END DESCRIPTION:
XS GIS Cut Line= 3
      2766355.68     10172353.11      2767225.39     10171394.29
      2767855.68     10170403.12
#Sta/Elev= 30
  3705.5 1449.50  3733.5 1443.37  3761.9 1440.49  3868.0 1435.03  4172.8 1433.42
  4215.4 1436.01  4250.5 1433.01  4831.6 1427.69  4944.6 1427.47  4987.2 1422.01
  5006.6 1421.78  5006.8 1421.28  5010.6 1421.78  5041.1 1425.68  5102.6 1430.80
  5190.7 1432.14  5275.3 1431.35  5369.3 1433.71  5572.5 1429.42  5653.4 1433.22
  5724.3 1438.17  5870.8 1440.62  5984.2 1444.26  6030.7 1445.23  6044.3 1448.48
  6051.8 1446.98  6124.7 1456.32  6151.7 1464.29  6160.3 1464.76  6174.6 1464.74
#Mann=9,-1,0
  3705.5    0.05       0  4831.6    0.12       0  5006.6    0.07       0
  5010.6    0.12       0  5041.1    0.05       0  5653.4    0.12       0
  5870.8    0.05       0  5984.2    0.12       0  6160.3    0.05       0
Bank Sta=5006.6,5010.6
Exp/Cntr=0.3,0.1

Type RM Length L Ch R = 1,65500,500,500,500
BEGIN DESCRIPTION:
BULLHEAD CREEK 131.0
END DESCRIPTION:
XS GIS Cut Line= 3
      2766898.76     10172564.10      2767647.92     10171545.29
      2767905.69     10171053.10
#Sta/Elev= 30
  3735.4 1427.50  3776.2 1426.22  3885.0 1427.25  3891.2 1426.34  4012.3 1426.17
  4070.9 1427.46  4098.0 1426.25  4313.2 1424.29  4449.0 1425.49  4469.8 1424.48
  4534.6 1424.66  4599.4 1422.80  4685.1 1421.96  4878.6 1424.24  4956.6 1422.85
  4977.9 1420.12  4992.1 1419.47  4996.3 1417.99  4996.5 1417.49  5000.3 1417.99
  5036.3 1424.04  5155.6 1424.02  5194.3 1425.21  5296.0 1425.67  5304.7 1424.64
  5310.3 1422.75  5318.5 1422.57  5354.4 1427.33  5457.4 1433.31  5555.6 1439.43
#Mann=5,-1,0
  3735.4    0.05       0  4996.3    0.05       0  5000.3    0.05       0
  5155.6    0.12       0  5457.4    0.05       0
Bank Sta=4996.3,5000.3
Exp/Cntr=0.3,0.1

Type RM Length L Ch R = 1,65000,500,500,500
BEGIN DESCRIPTION:
BULLHEAD CREEK 130.0
END DESCRIPTION:
XS GIS Cut Line= 3
      2767263.33     10172629.21      2767961.52     10171889.74
      2768155.69     10171653.11
#Sta/Elev= 30
  3983.0 1425.12  4130.3 1423.05  4180.1 1420.38  4215.3 1421.89  4265.0 1420.23
  4314.4 1415.64  4356.9 1419.34  4413.5 1420.32  4456.0 1420.03  4470.1 1418.12
  4484.3 1419.48  4491.2 1417.80  4498.5 1419.43  4519.5 1418.51  4540.9 1420.11
  4664.3 1419.07  4668.2 1418.80  4792.0 1418.78  4807.5 1418.71  4965.3 1418.81
  5006.3 1414.76  5006.5 1414.26  5010.3 1414.76  5029.1 1417.17  5086.2 1419.43
  5107.3 1421.77  5278.1 1430.97  5292.4 1433.08  5298.9 1437.92  5306.1 1437.56
#Mann=7,-1,0
  3983.0    0.05       0  4664.3    0.12       0  4668.2    0.05       0
  4792.0    0.12       0  4807.5    0.05       0  5006.3    0.05       0
  5010.3    0.05       0
Bank Sta=5006.3,5010.3
Exp/Cntr=0.3,0.1

Type RM Length L Ch R = 1,64500,500,500,500
BEGIN DESCRIPTION:
BULLHEAD CREEK 129.0
END DESCRIPTION:
XS GIS Cut Line= 3
      2767300.76     10172657.15      2768386.19     10172094.26
      2768952.17     10171336.74
#Sta/Elev= 30
  3777.3 1425.00  3997.5 1420.00  4308.0 1416.58  4334.6 1416.40  4362.3 1412.77
  4384.5 1416.29  4461.6 1416.45  4477.5 1417.10  4701.6 1416.48  4807.9 1417.37
  4904.2 1415.94  4920.6 1415.31  4932.0 1411.52  4942.8 1410.49  4954.4 1413.42
  4962.3 1413.51  4994.9 1410.16  4995.2 1409.66  4998.9 1410.16  5003.8 1410.16
  5028.4 1415.57  5042.9 1415.76  5107.6 1415.26  5157.7 1417.07  5264.0 1416.10
  5293.2 1414.72  5421.8 1414.55  5657.9 1416.45  5857.7 1423.70  5945.6 1426.11
#Mann=11,-1,0
  3777.3    0.05       0  4308.0    0.12       0  4461.6    0.05       0
  4477.5    0.12       0  4701.6    0.05       0  4962.3    0.12       0
  4994.9    0.07       0  4998.9    0.12       0  5042.9    0.05       0
  5421.8    0.12       0  5857.7    0.05       0
Bank Sta=4994.9,4998.9
Exp/Cntr=0.3,0.1

Type RM Length L Ch R = 1,64000,593,593,593
BEGIN DESCRIPTION:
BULLHEAD CREEK 128.0
END DESCRIPTION:
XS GIS Cut Line= 4
      2767355.25     10172697.20      2768319.24     10172286.14
      2768817.16     10172261.70      2769671.15     10171988.26
#Sta/Elev= 30
  3453.5 1425.42  3702.3 1418.59  3936.7 1416.10  3975.8 1414.29  3989.3 1412.06
  4012.9 1414.88  4042.0 1415.36  4149.7 1415.26  4212.8 1413.69  4337.1 1414.12
  4486.7 1416.06  4578.0 1415.59  4648.1 1413.64  4678.1 1414.14  4778.3 1411.60
  4902.9 1412.67  4948.5 1409.69  4994.7 1408.52  4995.0 1408.02  4998.8 1408.52
  5039.9 1413.42  5050.9 1416.54  5103.4 1420.29  5141.6 1421.37  5345.0 1422.90
  5500.4 1419.78  5537.8 1420.03  5618.0 1416.99  5666.4 1420.06  5896.7 1428.10
#Mann=5,-1,0
  3453.5    0.05       0  4337.1    0.12       0  4902.9    0.05       0
  4994.7    0.05       0  4998.8    0.05       0
Bank Sta=4994.7,4998.8
Exp/Cntr=0.3,0.1

Type RM Length L Ch R = 1,63407,407,407,407
BEGIN DESCRIPTION:
BULLHEAD CREEK 127.0
END DESCRIPTION:
XS GIS Cut Line= 4
      2767013.36     10173344.66      2768440.75     10172626.00
      2768741.95     10172590.87      2769665.15     10172231.57
#Sta/Elev= 30
  3401.9 1424.65  3681.1 1417.04  3827.1 1415.75  3887.5 1412.59  3919.5 1414.58
  4102.2 1413.73  4108.6 1414.14  4233.0 1415.98  4333.6 1413.49  4346.1 1413.67
  4378.6 1412.38  4618.1 1411.50  4826.4 1409.18  4871.2 1405.14  4925.1 1406.35
  4975.3 1405.19  4997.6 1403.91  4997.9 1402.46  4998.2 1401.96  5002.1 1402.46
  5105.6 1410.34  5226.5 1414.33  5276.8 1414.36  5296.9 1415.20  5302.6 1416.97
  5350.2 1415.66  5564.8 1418.36  5940.0 1412.88  6108.6 1419.99  6293.9 1425.16
#Mann=9,-1,0
  3401.9    0.05       0  3827.1    0.12       0  4102.2    0.05       0
  4108.6    0.12       0  4333.6    0.05       0  4346.1    0.12       0
  4618.1    0.05       0  4997.9    0.03       0  5002.1    0.05       0
Bank Sta=4997.9,5002.1
Exp/Cntr=0.3,0.1

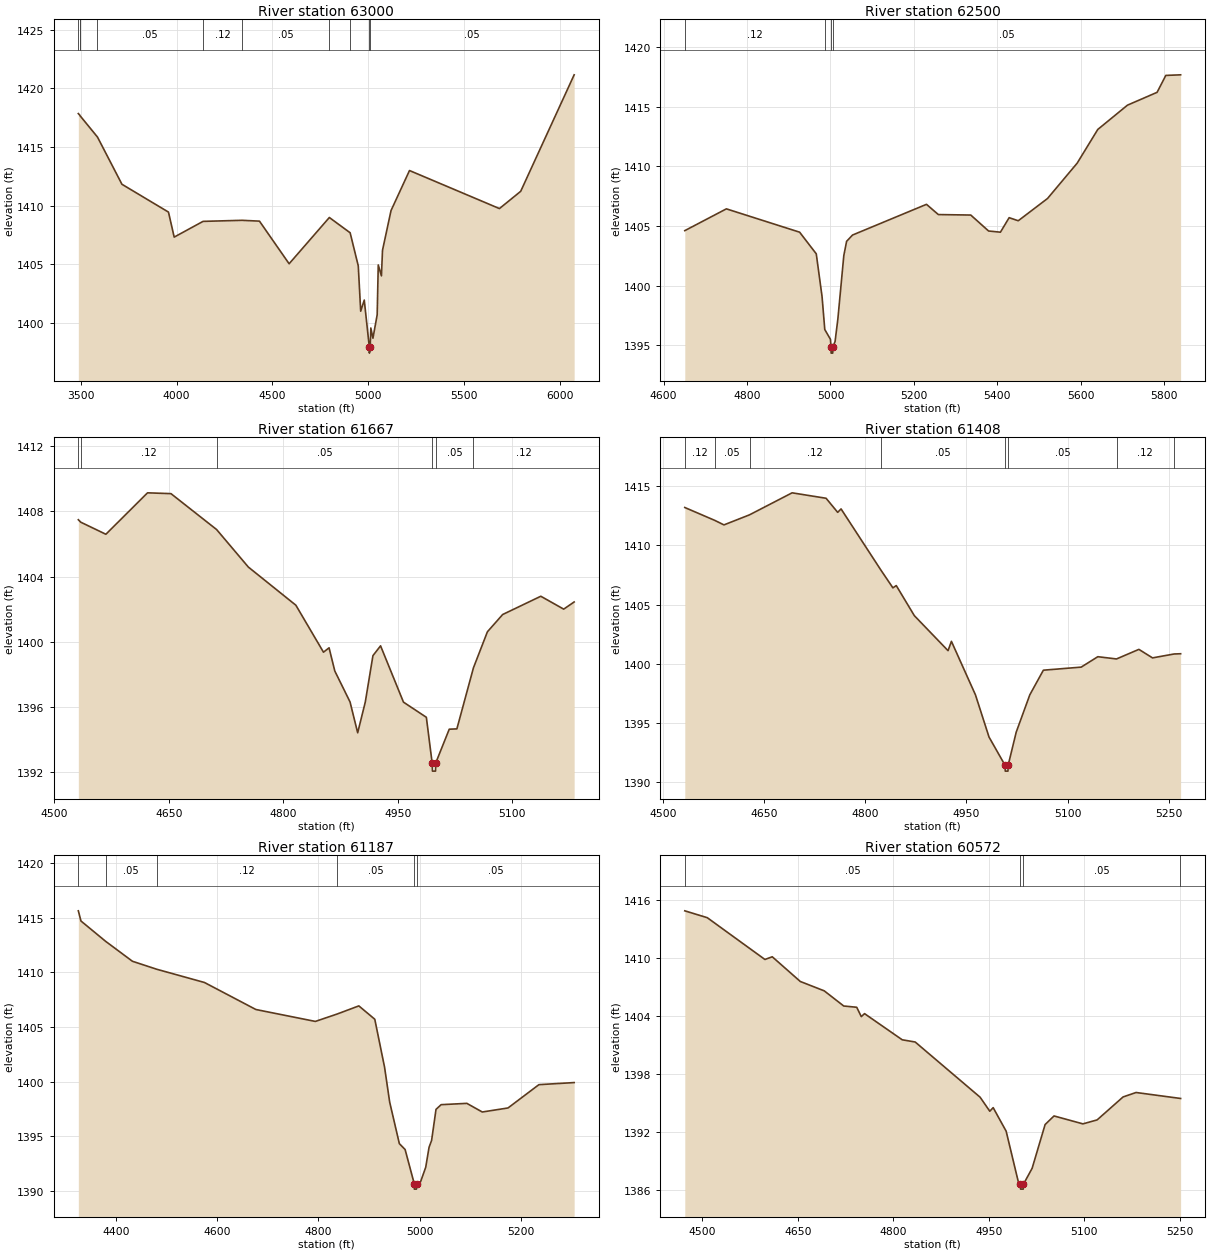
Type RM Length L Ch R = 1,63000,500,500,500
BEGIN DESCRIPTION:
BULLHEAD CREEK 126.0
END DESCRIPTION:
XS GIS Cut Line= 3
      2767272.27     10173495.40      2768673.21     10172922.11
      2769631.50     10172432.10
#Sta/Elev= 30
  3486.3 1417.85  3494.2 1417.71  3495.1 1417.67  3586.4 1415.85  3714.1 1411.83
  3957.2 1409.46  3987.0 1407.33  4137.9 1408.67  4341.8 1408.76  4432.5 1408.69
  4587.4 1405.06  4797.5 1409.00  4906.1 1407.70  4948.6 1404.88  4961.3 1401.02
  4979.9 1401.97  5006.4 1397.95  5006.7 1397.45  5010.8 1397.95  5014.2 1399.59
  5025.2 1398.72  5047.4 1400.72  5053.0 1404.96  5069.6 1404.03  5075.2 1406.21
  5119.7 1409.59  5216.2 1413.00  5686.0 1409.76  5797.1 1411.23  6076.3 1421.15
#Mann=10,-1,0
  3486.3    0.12       0  3494.2    0.05       0  3495.1    0.12       0
  3586.4    0.05       0  4137.9    0.12       0  4341.8    0.05       0
  4797.5    0.12       0  4906.1    0.05       0  5006.4    0.05       0
  5010.8    0.05       0
Bank Sta=5006.4,5010.8
Exp/Cntr=0.3,0.1

Type RM Length L Ch R = 1,62500,833,833,833
BEGIN DESCRIPTION:
BULLHEAD CREEK 125.0
END DESCRIPTION:
XS GIS Cut Line= 3
      2768703.18     10173389.89      2769027.21     10173259.74
      2769655.66     10172703.13
#Sta/Elev= 30
  4650.8 1404.61  4750.5 1406.44  4926.1 1404.48  4966.0 1402.66  4979.9 1399.06
  4986.4 1396.30  5000.0 1395.48  5001.3 1394.82  5001.6 1394.32  5005.4 1394.32
  5005.7 1394.82  5011.1 1395.30  5017.8 1397.20  5032.0 1402.51  5038.7 1403.71
  5052.9 1404.24  5230.2 1406.82  5258.7 1405.96  5336.4 1405.92  5379.1 1404.58
  5407.5 1404.48  5428.4 1405.70  5450.2 1405.44  5520.4 1407.31  5591.5 1410.28
  5640.9 1413.11  5712.0 1415.15  5783.1 1416.23  5804.0 1417.65  5839.5 1417.70
#Mann=4,-1,0
  4650.8    0.12       0  4986.4    0.05       0  5001.3    0.05       0
  5005.7    0.05       0
Bank Sta=5001.3,5005.7
Exp/Cntr=0.3,0.1

Type RM Length L Ch R = 1,61667,259,259,259
BEGIN DESCRIPTION:
Mapping XS 21605619
END DESCRIPTION:
XS GIS Cut Line= 3
      2768267.04     10173680.14      2768588.26     10173749.59
      2768909.42     10173749.59
#Sta/Elev= 30
  4531.5 1407.48  4534.7 1407.33  4567.6 1406.59  4622.2 1409.13  4652.9 1409.08
  4712.7 1406.88  4754.3 1404.58  4816.6 1402.24  4852.8 1399.36  4860.1 1399.63
  4867.6 1398.21  4887.6 1396.31  4897.6 1394.42  4907.6 1396.31  4917.6 1399.15
  4927.6 1399.75  4957.6 1396.30  4987.6 1395.37  4995.2 1392.57  4995.6 1392.07
  4999.6 1392.07  4999.9 1392.57  5017.6 1394.64  5027.6 1394.66  5049.3 1398.40
  5067.6 1400.61  5087.6 1401.67  5137.6 1402.79  5167.6 1402.00  5181.3 1402.44
#Mann=6,-1,0
  4531.5    0.05       0  4534.7    0.12       0  4712.7    0.05       0
  4995.2    0.05       0  4999.9    0.05       0  5049.3    0.12       0
Bank Sta=4995.2,4999.9
Exp/Cntr=0.3,0.1

Type RM Length L Ch R = 1,61408,221,221,221
BEGIN DESCRIPTION:
Mapping XS dcf0b095
END DESCRIPTION:
XS GIS Cut Line= 3
      2768197.64     10173940.56      2768770.55     10174010.01
      2768926.79     10173983.97
#Sta/Elev= 30
  4532.2 1413.21  4576.7 1412.12  4590.3 1411.74  4628.2 1412.59  4691.4 1414.45
  4741.8 1413.99  4759.0 1412.80  4764.0 1413.09  4823.1 1407.92  4840.9 1406.42
  4845.9 1406.61  4872.7 1404.07  4922.7 1401.11  4927.7 1401.90  4963.4 1397.37
  4983.5 1393.81  5007.2 1391.43  5007.6 1390.93  5011.6 1390.93  5011.9 1391.43
  5023.8 1394.22  5044.0 1397.38  5064.1 1399.46  5120.2 1399.72  5144.9 1400.60
  5172.6 1400.41  5205.8 1401.22  5226.0 1400.50  5258.0 1400.83  5267.7 1400.85
#Mann=8,-1,0
  4532.2    0.12       0  4576.7    0.05       0  4628.2    0.12       0
  4823.1    0.05       0  5007.2    0.05       0  5011.9    0.05       0
  5172.6    0.12       0  5258.0    0.05       0
Bank Sta=5007.2,5011.9
Exp/Cntr=0.3,0.1

Type RM Length L Ch R = 1,61187,615,615,615
BEGIN DESCRIPTION:
Mapping XS d5821286
END DESCRIPTION:
XS GIS Cut Line= 2
      2767980.60     10174331.19      2768944.18     10174157.57
#Sta/Elev= 30
  4326.0 1415.61  4331.2 1414.68  4379.7 1412.83  4432.8 1411.00  4480.8 1410.27
  4575.0 1409.06  4676.6 1406.59  4794.0 1405.50  4836.7 1406.17  4879.9 1406.92
  4911.4 1405.70  4930.7 1401.32  4940.8 1398.13  4959.9 1394.33  4971.3 1393.79
  4989.3 1390.67  4989.6 1390.17  4993.6 1390.17  4994.0 1390.67  5001.8 1390.84
  5012.0 1392.17  5018.6 1394.00  5023.6 1394.62  5032.3 1397.46  5042.4 1397.89
  5093.2 1398.01  5123.7 1397.22  5174.5 1397.59  5235.5 1399.72  5305.1 1399.91
#Mann=6,-1,0
  4326.0    0.12       0  4379.7    0.05       0  4480.8    0.12       0
  4836.7    0.05       0  4989.3    0.05       0  4994.0    0.05       0
Bank Sta=4989.3,4994
Exp/Cntr=0.3,0.1

Type RM Length L Ch R = 1,60572,594,594,594
BEGIN DESCRIPTION:
Mapping XS fe90b5ae
END DESCRIPTION:
XS GIS Cut Line= 2
      2768241.05     10174904.10      2769004.25     10174747.99
#Sta/Elev= 30
  4472.4 1414.89  4507.7 1414.18  4598.3 1409.85  4609.8 1410.13  4653.9 1407.57
  4691.5 1406.60  4722.1 1405.03  4742.5 1404.90  4749.7 1403.93  4754.8 1404.24
  4814.0 1401.53  4834.4 1401.30  4936.4 1395.58  4951.6 1394.13  4956.9 1394.50
  4977.3 1392.06  4996.9 1386.68  4999.6 1386.56  5000.0 1386.06  5004.1 1386.06
  5004.4 1386.56  5018.1 1388.22  5038.5 1392.75  5052.5 1393.64  5097.9 1392.82
  5120.2 1393.23  5161.0 1395.61  5181.4 1396.07  5250.4 1395.46  5251.4 1395.45
#Mann=4,-1,0
  4472.4    0.05       0  4999.6    0.05       0  5004.4    0.05       0
  5250.4    0.12       0
Bank Sta=4999.6,5004.4
Exp/Cntr=0.3,0.1