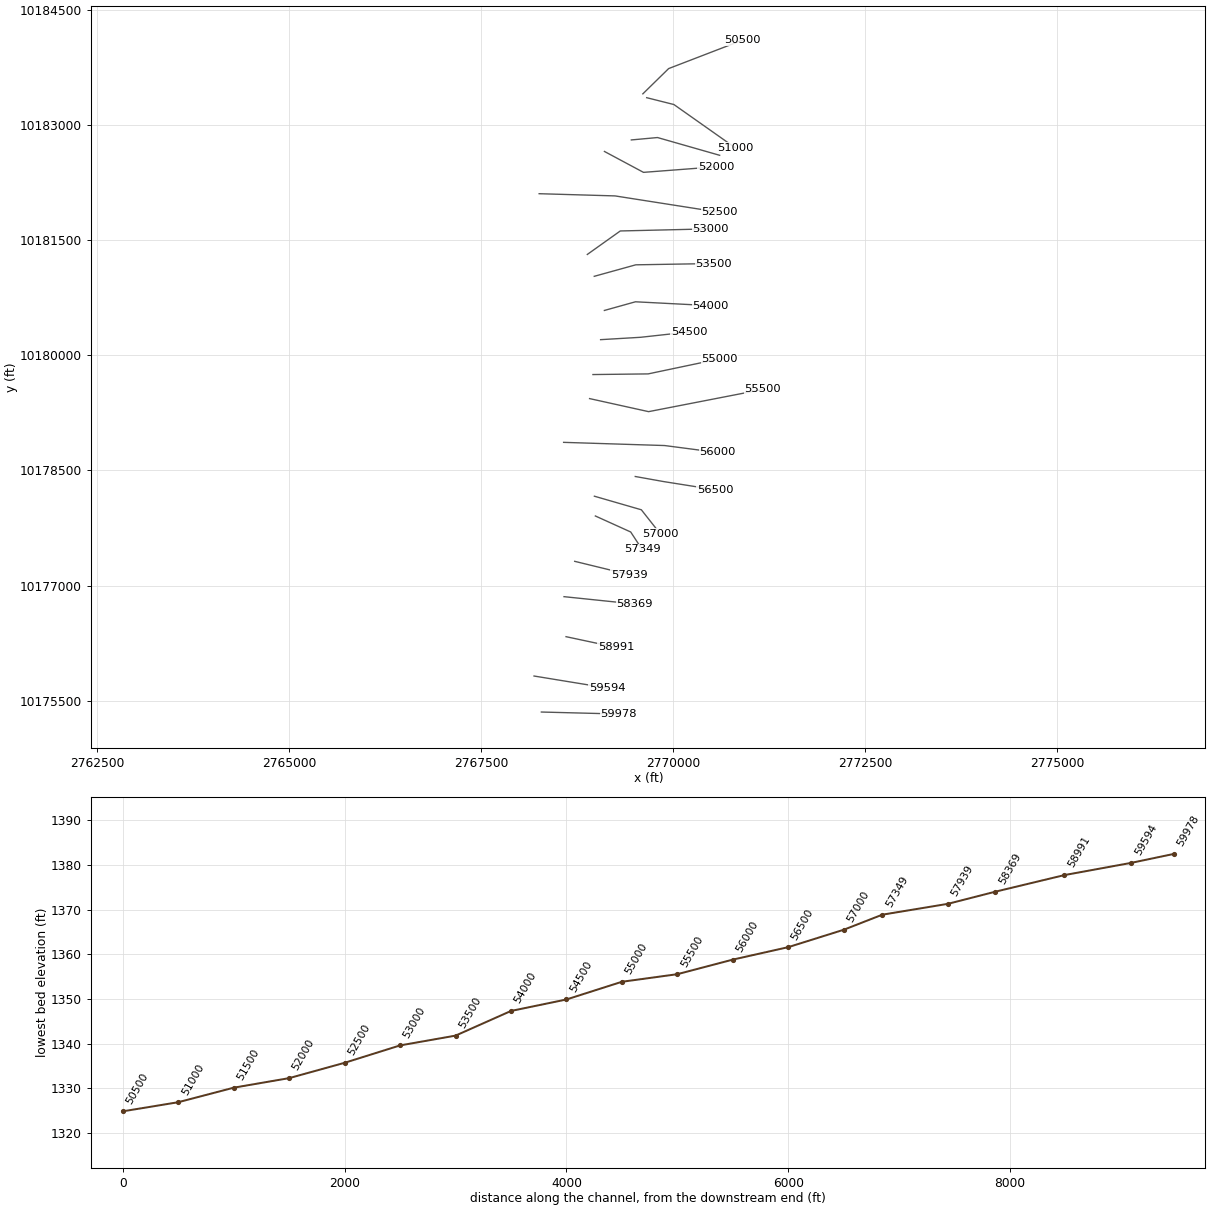
HEC-RAS study BULLHEAD CREEK.prj: BULLHEAD CREEK Base Level Engineering

--- BULLHEAD CREEK.g01 (geometry) --- (continued)

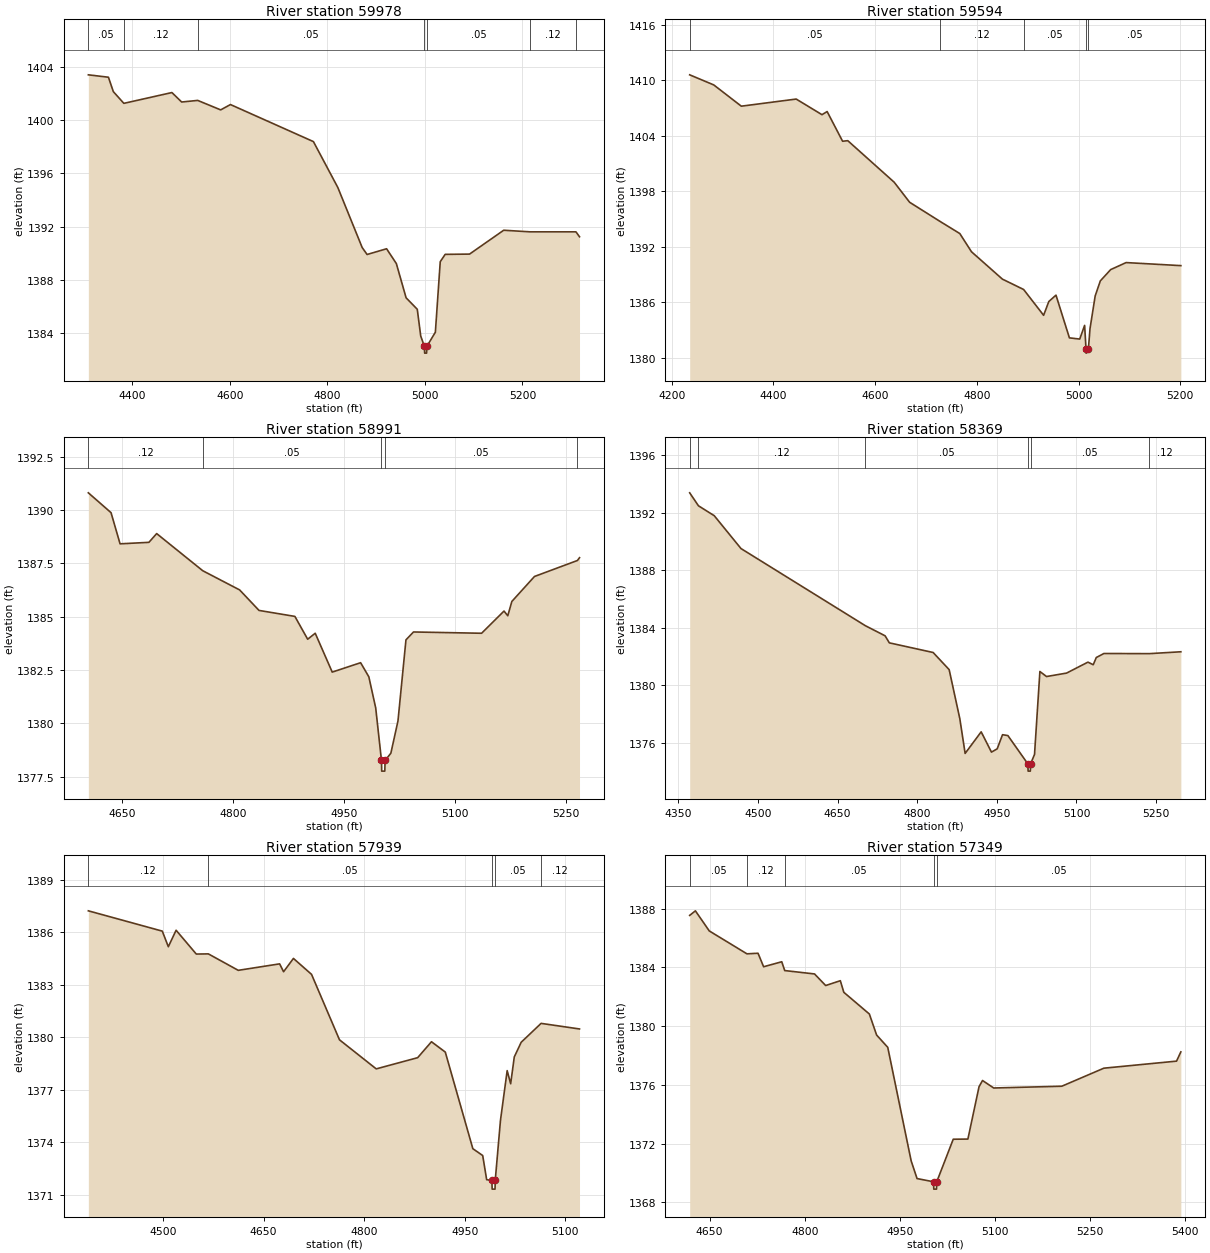
Type RM Length L Ch R = 1,59978,384,384,384
BEGIN DESCRIPTION:
Mapping XS 5dc540f4
END DESCRIPTION:
XS GIS Cut Line= 2
      2768284.48     10175355.49      2769291.04     10175329.46
#Sta/Elev= 30
  4310.0 1403.38  4351.2 1403.20  4361.2 1402.12  4382.8 1401.24  4481.3 1402.05
  4501.3 1401.34  4534.2 1401.46  4581.3 1400.75  4601.3 1401.15  4771.4 1398.37
  4821.4 1394.93  4871.4 1390.42  4881.4 1389.90  4921.4 1390.33  4941.4 1389.22
  4961.4 1386.65  4984.3 1385.79  4991.4 1383.78  4999.0 1383.00  4999.4 1382.50
  5003.5 1382.50  5003.8 1383.00  5021.4 1384.07  5031.4 1389.36  5041.5 1389.91
  5091.5 1389.93  5161.5 1391.72  5215.4 1391.60  5309.6 1391.60  5316.9 1391.23
#Mann=7,-1,0
  4310.0    0.05       0  4382.8    0.12       0  4534.2    0.05       0
  4999.0    0.05       0  5003.8    0.05       0  5215.4    0.12       0
  5309.6    0.05       0
Bank Sta=4999,5003.8
Exp/Cntr=0.3,0.1

Type RM Length L Ch R = 1,59594,603,603,603
BEGIN DESCRIPTION:
Mapping XS 9373c020
END DESCRIPTION:
XS GIS Cut Line= 2
      2768188.99     10175824.24      2769141.91     10175668.30
#Sta/Elev= 30
  4235.4 1410.59  4282.7 1409.50  4336.9 1407.20  4444.8 1407.97  4495.5 1406.28
  4505.6 1406.62  4536.0 1403.41  4546.2 1403.47  4637.4 1398.98  4667.8 1396.81
  4727.6 1394.74  4766.4 1393.43  4789.4 1391.46  4850.2 1388.50  4891.9 1387.38
  4931.2 1384.59  4941.4 1386.08  4955.5 1386.77  4981.9 1382.15  5002.2 1382.02
  5011.8 1383.50  5014.5 1381.00  5014.8 1380.50  5019.3 1381.00  5022.4 1383.14
  5032.6 1386.69  5042.7 1388.31  5063.0 1389.53  5093.4 1390.29  5201.0 1389.96
#Mann=5,-1,0
  4235.4    0.05       0  4727.6    0.12       0  4891.9    0.05       0
  5014.5    0.05       0  5019.3    0.05       0
Bank Sta=5014.5,5019.3
Exp/Cntr=0.3,0.1

Type RM Length L Ch R = 1,58991,622,622,622
BEGIN DESCRIPTION:
Mapping XS 197ee3eb
END DESCRIPTION:
XS GIS Cut Line= 2
      2768605.63     10176336.39      2769255.21     10176197.82
#Sta/Elev= 30
  4604.3 1390.80  4635.0 1389.87  4647.2 1388.41  4686.2 1388.48  4696.7 1388.89
  4759.0 1387.15  4808.9 1386.25  4835.1 1385.29  4883.6 1385.01  4900.9 1383.94
  4911.1 1384.22  4934.1 1382.40  4972.5 1382.84  4983.6 1382.18  4992.9 1380.72
  5000.7 1378.26  5001.0 1377.76  5005.2 1377.76  5005.6 1378.26  5013.4 1378.60
  5023.0 1380.11  5033.8 1383.91  5044.0 1384.28  5136.1 1384.22  5166.4 1385.26
  5171.5 1385.04  5177.0 1385.71  5207.6 1386.88  5265.7 1387.63  5268.5 1387.76
#Mann=5,-1,0
  4604.3    0.12       0  4759.0    0.05       0  5000.7    0.05       0
  5005.6    0.05       0  5265.7    0.12       0
Bank Sta=5000.7,5005.6
Exp/Cntr=0.3,0.1

Type RM Length L Ch R = 1,58369,430,430,430
BEGIN DESCRIPTION:
Mapping XS ea998262
END DESCRIPTION:
XS GIS Cut Line= 2
      2768579.61     10176857.23      2769499.77     10176761.74
#Sta/Elev= 30
  4371.5 1393.38  4388.0 1392.48  4417.8 1391.79  4468.1 1389.51  4702.4 1384.15
  4739.5 1383.45  4747.5 1382.96  4830.0 1382.29  4860.2 1381.10  4880.3 1377.69
  4890.3 1375.28  4920.5 1376.78  4939.9 1375.37  4950.7 1375.60  4960.7 1376.58
  4970.8 1376.52  5008.5 1374.55  5008.9 1374.05  5013.1 1374.05  5013.5 1374.55
  5021.0 1375.21  5031.1 1380.97  5043.6 1380.62  5081.4 1380.86  5121.6 1381.62
  5131.6 1381.44  5137.3 1381.94  5151.7 1382.22  5237.0 1382.21  5296.6 1382.34
#Mann=6,-1,0
  4371.5    0.05       0  4388.0    0.12       0  4702.4    0.05       0
  5008.5    0.05       0  5013.5    0.05       0  5237.0    0.12       0
Bank Sta=5008.5,5013.5
Exp/Cntr=0.3,0.1

Type RM Length L Ch R = 1,57939,590,590,590
BEGIN DESCRIPTION:
Mapping XS f1cfa42e
END DESCRIPTION:
XS GIS Cut Line= 2
      2768718.49     10177317.29      2769430.23     10177143.70
#Sta/Elev= 30
  4388.6 1387.22  4498.9 1386.06  4507.9 1385.17  4519.5 1386.11  4549.6 1384.75
  4567.6 1384.76  4612.2 1383.82  4673.9 1384.19  4679.8 1383.74  4694.5 1384.50
  4721.5 1383.59  4763.2 1379.85  4818.0 1378.19  4879.8 1378.83  4900.4 1379.74
  4921.0 1379.15  4962.1 1373.63  4976.8 1373.24  4982.7 1371.86  4990.5 1371.82
  4990.9 1371.32  4995.2 1371.32  4995.5 1371.82  5003.3 1375.25  5013.3 1378.09
  5018.5 1377.34  5023.9 1378.87  5034.2 1379.71  5063.9 1380.79  5121.2 1380.47
#Mann=5,-1,0
  4388.6    0.12       0  4567.6    0.05       0  4990.5    0.05       0
  4995.5    0.05       0  5063.9    0.12       0
Bank Sta=4990.5,4995.5
Exp/Cntr=0.3,0.1

Type RM Length L Ch R = 1,57349,349,349,349
BEGIN DESCRIPTION:
Mapping XS 2b40b98a
END DESCRIPTION:
XS GIS Cut Line= 3
      2768987.53     10177907.59      2769447.63     10177699.24
      2769595.18     10177473.58
#Sta/Elev= 30
  4618.5 1387.55  4627.5 1387.86  4649.4 1386.49  4708.8 1384.93  4726.3 1384.97
  4735.1 1384.05  4763.7 1384.39  4768.4 1383.79  4815.4 1383.56  4833.0 1382.77
  4856.1 1383.10  4861.6 1382.31  4901.9 1380.83  4913.3 1379.40  4930.9 1378.56
  4967.8 1370.83  4977.1 1369.62  5003.1 1369.40  5003.5 1368.90  5007.8 1368.90
  5008.2 1369.40  5034.2 1372.30  5057.3 1372.31  5074.9 1375.88  5080.4 1376.30
  5098.0 1375.79  5205.4 1375.91  5271.8 1377.14  5386.4 1377.62  5393.2 1378.25
#Mann=5,-1,0
  4618.5    0.05       0  4708.8    0.12       0  4768.4    0.05       0
  5003.1    0.05       0  5008.2    0.05       0
Bank Sta=5003.1,5008.2
Exp/Cntr=0.3,0.1

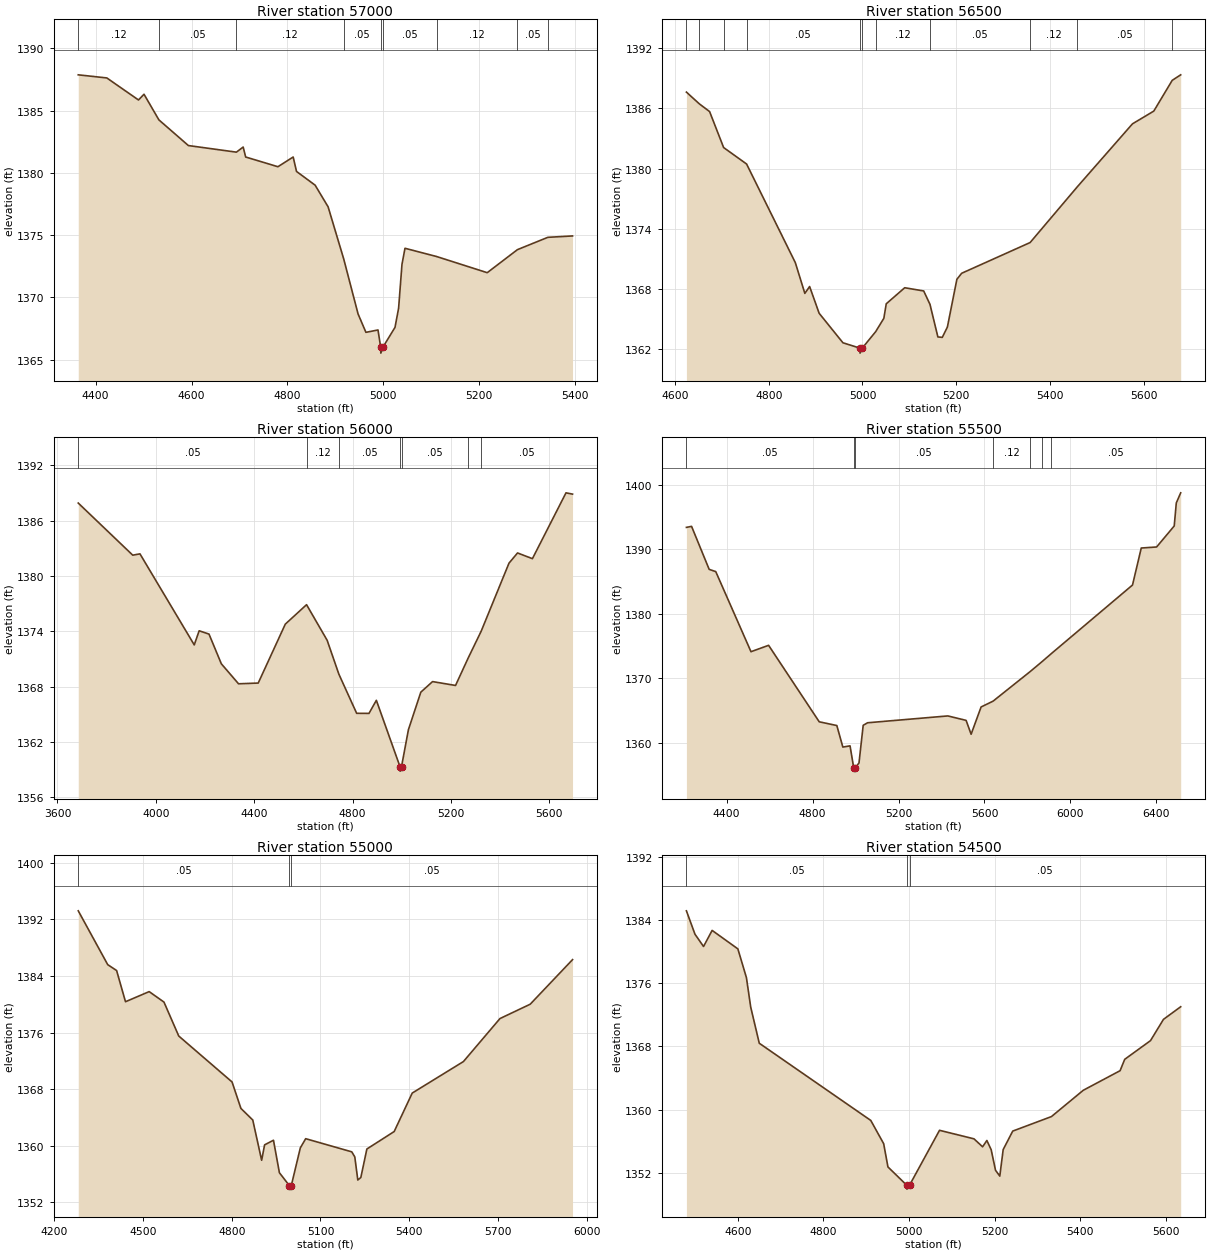
Type RM Length L Ch R = 1,57000,500,500,500
BEGIN DESCRIPTION:
BULLHEAD CREEK 114.0
END DESCRIPTION:
XS GIS Cut Line= 3
      2768974.89     10178165.09      2769586.15     10177988.33
      2769830.68     10177678.12
#Sta/Elev= 30
  4363.7 1387.87  4423.3 1387.62  4489.4 1385.85  4500.9 1386.31  4532.0 1384.25
  4593.5 1382.19  4693.7 1381.66  4707.8 1382.07  4713.0 1381.27  4780.3 1380.49
  4812.1 1381.27  4819.1 1380.11  4857.9 1379.01  4885.0 1377.27  4917.6 1373.08
  4947.5 1368.67  4963.9 1367.19  4989.1 1367.38  4994.6 1366.02  4995.0 1365.52
  4999.7 1366.02  5024.6 1367.59  5032.1 1369.13  5039.1 1372.64  5045.4 1373.94
  5111.2 1373.28  5217.0 1371.98  5280.0 1373.83  5343.5 1374.82  5395.0 1374.93
#Mann=9,-1,0
  4363.7    0.12       0  4532.0    0.05       0  4693.7    0.12       0
  4917.6    0.05       0  4994.6    0.03       0  4999.7    0.05       0
  5111.2    0.12       0  5280.0    0.05       0  5343.5    0.12       0
Bank Sta=4994.6,4999.7
Exp/Cntr=0.3,0.1

Type RM Length L Ch R = 1,56500,500,500,500
BEGIN DESCRIPTION:
BULLHEAD CREEK 113.0
END DESCRIPTION:
XS GIS Cut Line= 3
      2769506.93     10178421.74      2769876.74     10178355.44
      2770547.36     10178249.11
#Sta/Elev= 30
  4624.3 1387.62  4651.6 1386.46  4673.8 1385.68  4703.7 1382.10  4752.7 1380.46
  4856.7 1370.64  4877.0 1367.58  4887.2 1368.26  4907.5 1365.60  4958.3 1362.66
  4994.4 1362.13  4994.8 1361.63  4999.5 1362.13  5028.2 1363.77  5045.6 1365.10
  5050.7 1366.54  5090.1 1368.14  5130.6 1367.82  5144.0 1366.49  5160.9 1363.24
  5170.3 1363.20  5181.2 1364.23  5201.4 1368.98  5211.6 1369.58  5357.7 1372.64
  5458.4 1378.19  5576.1 1384.46  5621.6 1385.73  5660.9 1388.79  5679.0 1389.34
#Mann=11,-1,0
  4624.3    0.12       0  4651.6    0.05       0  4703.7    0.12       0
  4752.7    0.05       0  4994.4    0.05       0  4999.5    0.05       0
  5028.2    0.12       0  5144.0    0.05       0  5357.7    0.12       0
  5458.4    0.05       0  5660.9    0.12       0
Bank Sta=4994.4,4999.5
Exp/Cntr=0.3,0.1

Type RM Length L Ch R = 1,56000,500,500,500
BEGIN DESCRIPTION:
BULLHEAD CREEK 112.0
END DESCRIPTION:
XS GIS Cut Line= 3
      2768574.31     10178866.17      2769888.95     10178824.65
      2770577.40     10178734.71
#Sta/Elev= 30
  3684.7 1387.91  3906.2 1382.26  3935.6 1382.40  4156.3 1372.53  4176.3 1374.06
  4216.3 1373.70  4266.4 1370.48  4336.4 1368.31  4416.4 1368.39  4526.5 1374.78
  4612.9 1376.89  4696.6 1373.03  4744.2 1369.36  4816.6 1365.11  4866.7 1365.10
  4896.7 1366.52  4992.6 1359.34  4993.1 1358.84  4999.1 1359.34  5027.0 1363.33
  5077.4 1367.40  5125.2 1368.55  5218.6 1368.13  5269.9 1371.10  5322.8 1374.01
  5435.9 1381.39  5470.7 1382.50  5531.2 1381.88  5667.7 1389.02  5694.3 1388.88
#Mann=7,-1,0
  3684.7    0.05       0  4612.9    0.12       0  4744.2    0.05       0
  4992.6    0.05       0  4999.1    0.05       0  5269.9    0.12       0
  5322.8    0.05       0
Bank Sta=4992.6,4999.1
Exp/Cntr=0.3,0.1

Type RM Length L Ch R = 1,55500,500,500,500
BEGIN DESCRIPTION:
BULLHEAD CREEK 111.0
END DESCRIPTION:
XS GIS Cut Line= 3
      2768912.26     10179435.81      2769680.59     10179265.87
      2771165.76     10179554.73
#Sta/Elev= 30
  4213.1 1393.38  4237.1 1393.54  4319.0 1386.87  4349.7 1386.52  4513.6 1374.10
  4595.5 1375.09  4831.1 1363.23  4913.0 1362.65  4941.0 1359.31  4974.5 1359.50
  4991.6 1356.08  4992.1 1355.58  4998.2 1356.08  5016.1 1356.84  5035.7 1362.69
  5056.1 1363.08  5429.4 1364.14  5514.6 1363.45  5537.8 1361.30  5584.3 1365.53
  5639.9 1366.43  5811.9 1371.00  5867.5 1372.55  5911.6 1373.82  6288.8 1384.44
  6329.5 1390.18  6400.9 1390.34  6482.9 1393.60  6492.5 1397.17  6513.0 1398.74
#Mann=7,-1,0
  4213.1    0.05       0  4991.6    0.05       0  4998.2    0.05       0
  5639.9    0.12       0  5811.9    0.05       0  5867.5    0.12       0
  5911.6    0.05       0
Bank Sta=4991.6,4998.2
Exp/Cntr=0.3,0.1

Type RM Length L Ch R = 1,55000,500,500,500
BEGIN DESCRIPTION:
BULLHEAD CREEK 110.0
END DESCRIPTION:
XS GIS Cut Line= 3
      2768956.08     10179748.78      2769674.43     10179757.27
      2770605.66     10179953.11
#Sta/Elev= 30
  4281.6 1393.22  4381.2 1385.61  4411.2 1384.78  4441.2 1380.37  4521.2 1381.80
  4571.2 1380.32  4621.2 1375.52  4801.2 1369.03  4831.2 1365.29  4871.2 1363.65
  4901.2 1357.96  4911.2 1360.14  4941.2 1360.79  4961.2 1356.20  4994.8 1354.38
  4995.3 1353.88  5001.4 1354.38  5031.9 1359.71  5050.0 1361.01  5205.7 1359.15
  5215.9 1358.44  5226.1 1355.17  5236.3 1355.52  5256.7 1359.55  5349.0 1362.02
  5410.0 1367.46  5582.9 1371.91  5706.4 1377.99  5808.6 1380.02  5951.6 1386.32
#Mann=3,-1,0
  4281.6    0.05       0  4994.8    0.05       0  5001.4    0.05       0
Bank Sta=4994.8,5001.4
Exp/Cntr=0.3,0.1

Type RM Length L Ch R = 1,54500,500,500,500
BEGIN DESCRIPTION:
BULLHEAD CREEK 109.0
END DESCRIPTION:
XS GIS Cut Line= 3
      2769055.73     10180203.11      2769574.93     10180233.79
      2770205.73     10180303.12
#Sta/Elev= 30
  4479.9 1385.17  4499.9 1382.21  4519.9 1380.65  4540.0 1382.69  4600.1 1380.35
  4620.1 1376.71  4630.1 1372.98  4650.1 1368.40  4910.6 1358.62  4940.7 1355.68
  4950.7 1352.73  4994.5 1350.42  4995.0 1349.92  5001.2 1350.42  5071.2 1357.37
  5151.7 1356.29  5171.8 1355.28  5181.8 1356.08  5191.9 1354.91  5202.0 1352.31
  5212.0 1351.57  5219.9 1354.93  5242.2 1357.27  5332.7 1359.11  5407.0 1362.44
  5493.0 1364.92  5503.8 1366.36  5564.1 1368.73  5594.3 1371.42  5634.6 1373.02
#Mann=3,-1,0
  4479.9    0.05       0  4994.5    0.05       0  5001.2    0.05       0
Bank Sta=4994.5,5001.2
Exp/Cntr=0.3,0.1

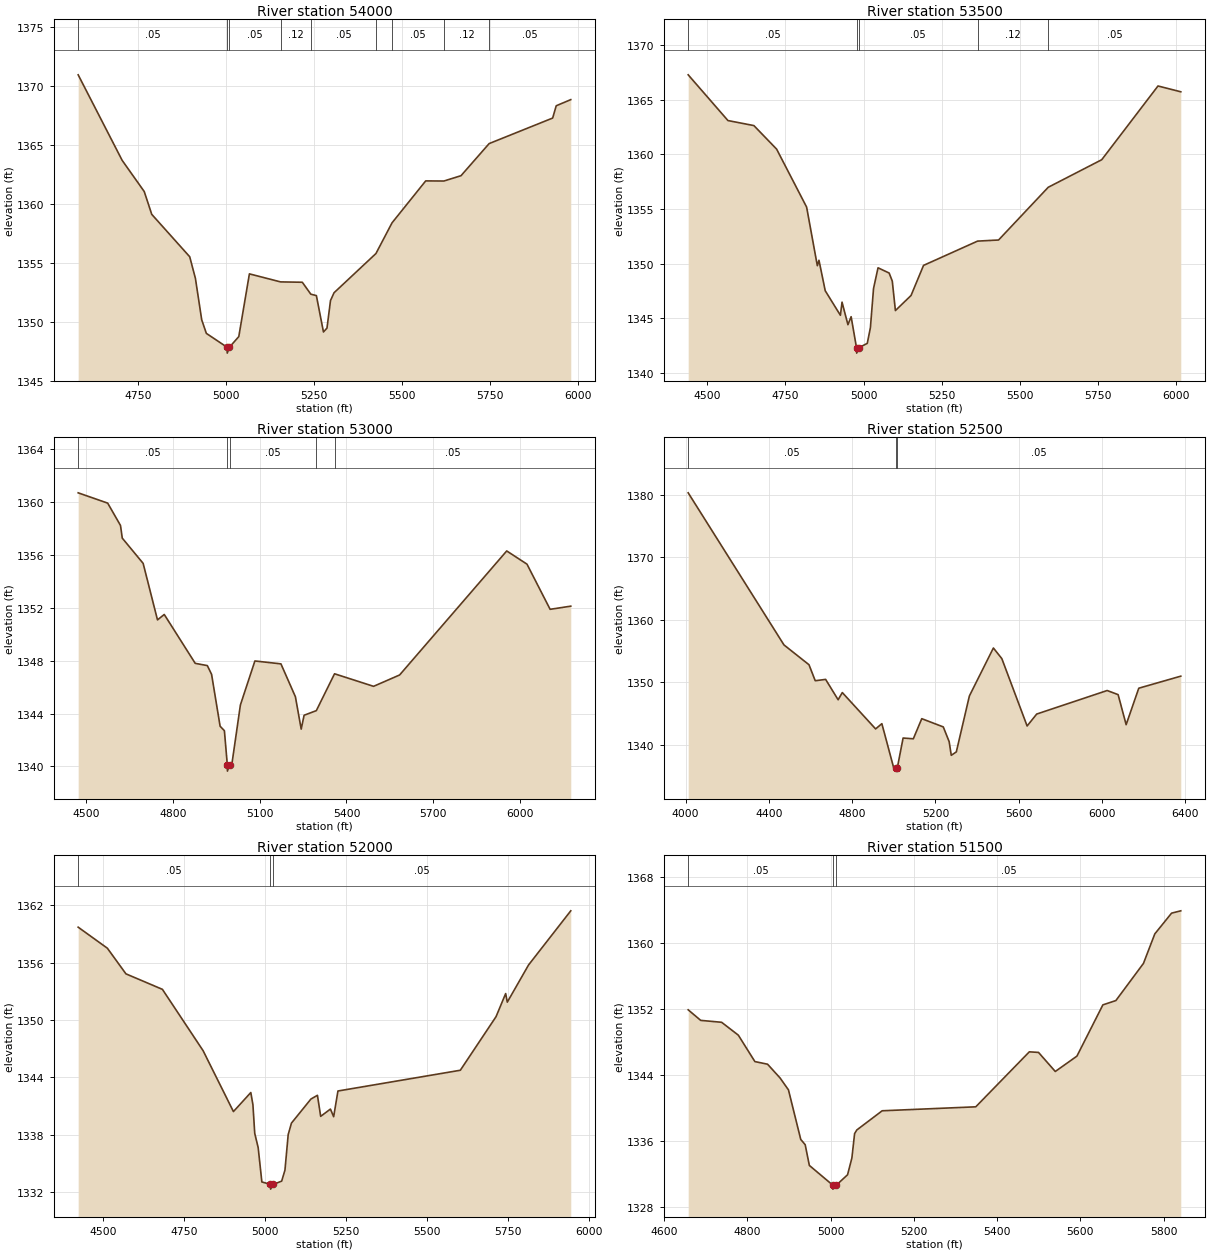
Type RM Length L Ch R = 1,54000,500,500,500
BEGIN DESCRIPTION:
BULLHEAD CREEK 108.0
END DESCRIPTION:
XS GIS Cut Line= 3
      2769105.02     10180583.24      2769509.49     10180696.02
      2770487.00     10180645.74
#Sta/Elev= 30
  4580.1 1370.91  4705.0 1363.67  4767.7 1361.03  4789.0 1359.10  4896.8 1355.51
  4913.0 1353.68  4930.9 1350.17  4944.1 1349.02  5002.9 1347.85  5003.4 1347.35
  5009.6 1347.85  5036.2 1348.75  5066.3 1354.06  5154.8 1353.38  5216.5 1353.35
  5240.7 1352.34  5256.5 1352.22  5276.6 1349.14  5286.6 1349.47  5296.6 1351.80
  5306.6 1352.46  5425.6 1355.78  5471.3 1358.38  5566.9 1361.93  5618.6 1361.92
  5667.1 1362.37  5747.1 1365.09  5927.4 1367.25  5937.5 1368.29  5978.8 1368.81
#Mann=9,-1,0
  4580.1    0.05       0  5002.9    0.05       0  5009.6    0.05       0
  5154.8    0.12       0  5240.7    0.05       0  5425.6    0.12       0
  5471.3    0.05       0  5618.6    0.12       0  5747.1    0.05       0
Bank Sta=5002.9,5009.6
Exp/Cntr=0.3,0.1

Type RM Length L Ch R = 1,53500,500,500,500
BEGIN DESCRIPTION:
BULLHEAD CREEK 107.0
END DESCRIPTION:
XS GIS Cut Line= 3
      2768973.07     10181027.69      2769513.64     10181177.34
      2770528.59     10181194.35
#Sta/Elev= 30
  4439.1 1367.27  4566.3 1363.09  4649.3 1362.63  4722.0 1360.48  4818.0 1355.18
  4852.3 1349.82  4857.5 1350.32  4877.6 1347.53  4926.1 1345.29  4931.3 1346.49
  4950.2 1344.43  4960.4 1345.16  4977.6 1342.33  4978.1 1341.83  4985.2 1342.33
  5012.0 1342.72  5022.1 1344.16  5032.1 1347.74  5046.5 1349.63  5082.1 1349.15
  5092.1 1348.41  5102.1 1345.72  5152.1 1347.10  5192.1 1349.85  5365.0 1352.07
  5432.1 1352.17  5591.0 1356.99  5762.2 1359.51  5942.2 1366.25  6015.1 1365.72
#Mann=5,-1,0
  4439.1    0.05       0  4977.6    0.05       0  4985.2    0.05       0
  5365.0    0.12       0  5591.0    0.05       0
Bank Sta=4977.6,4985.2
Exp/Cntr=0.3,0.1

Type RM Length L Ch R = 1,53000,500,500,500
BEGIN DESCRIPTION:
BULLHEAD CREEK 106.0
END DESCRIPTION:
XS GIS Cut Line= 3
      2768882.77     10181312.40      2769312.16     10181618.12
      2770486.93     10181645.74
#Sta/Elev= 30
  4472.9 1360.71  4574.9 1359.93  4619.2 1358.24  4625.3 1357.28  4697.4 1355.37
  4747.0 1351.09  4770.4 1351.50  4877.4 1347.80  4919.2 1347.63  4933.9 1346.97
  4963.4 1343.04  4978.2 1342.70  4988.2 1340.14  4988.7 1339.64  4995.9 1340.14
  5004.3 1340.21  5033.5 1344.65  5083.6 1347.98  5173.6 1347.76  5223.6 1345.27
  5243.6 1342.82  5253.6 1343.87  5295.9 1344.22  5358.8 1347.01  5493.7 1346.06
  5583.7 1346.92  5953.8 1356.31  6023.8 1355.31  6103.8 1351.89  6175.1 1352.13
#Mann=5,-1,0
  4472.9    0.05       0  4988.2    0.03       0  4995.9    0.05       0
  5295.9    0.12       0  5358.8    0.05       0
Bank Sta=4988.2,4995.9
Exp/Cntr=0.3,0.1

Type RM Length L Ch R = 1,52500,500,500,500
BEGIN DESCRIPTION:
BULLHEAD CREEK 105.0
END DESCRIPTION:
XS GIS Cut Line= 3
      2768255.64     10182103.11      2769243.13     10182074.45
      2770605.00     10181861.02
#Sta/Elev= 30
  4012.1 1380.32  4472.3 1355.96  4592.4 1352.79  4622.4 1350.23  4672.4 1350.44
  4732.4 1347.18  4752.5 1348.33  4912.5 1342.51  4942.5 1343.35  4998.8 1336.35
  5008.8 1336.25  5009.3 1335.75  5016.6 1336.25  5044.5 1341.05  5093.7 1340.93
  5134.2 1344.15  5237.6 1342.83  5265.8 1340.47  5275.9 1338.28  5300.2 1338.83
  5362.9 1347.78  5478.3 1355.47  5518.8 1353.77  5640.3 1342.98  5686.3 1344.89
  6024.9 1348.66  6077.5 1348.00  6116.0 1343.19  6176.7 1349.03  6378.5 1350.96
#Mann=3,-1,0
  4012.1    0.05       0  5008.8    0.05       0  5016.6    0.05       0
Bank Sta=5008.8,5016.6
Exp/Cntr=0.3,0.1

Type RM Length L Ch R = 1,52000,500,500,500
BEGIN DESCRIPTION:
BULLHEAD CREEK 104.0
END DESCRIPTION:
XS GIS Cut Line= 3
      2769105.66     10182653.13      2769613.90     10182381.03
      2770555.65     10182453.11
#Sta/Elev= 30
  4423.5 1359.71  4513.7 1357.51  4571.0 1354.83  4683.6 1353.21  4809.2 1346.80
  4902.9 1340.43  4956.6 1342.42  4963.1 1341.14  4968.7 1338.15  4979.3 1336.66
  4990.7 1333.07  5017.2 1332.82  5017.7 1332.32  5026.5 1332.82  5051.9 1333.16
  5062.0 1334.31  5072.0 1338.02  5082.0 1339.22  5142.2 1341.74  5162.3 1342.13
  5172.3 1339.93  5202.4 1340.69  5212.4 1339.89  5225.6 1342.58  5603.5 1344.75
  5713.9 1350.36  5743.5 1352.77  5748.5 1351.87  5814.2 1355.76  5944.5 1361.42
#Mann=3,-1,0
  4423.5    0.05       0  5017.2    0.03       0  5026.5    0.05       0
Bank Sta=5017.2,5026.5
Exp/Cntr=0.3,0.1

Type RM Length L Ch R = 1,51500,500,500,500
BEGIN DESCRIPTION:
BULLHEAD CREEK 103.0
END DESCRIPTION:
XS GIS Cut Line= 3
      2769455.68     10182803.11      2769796.66     10182834.26
      2770605.69     10182603.11
#Sta/Elev= 30
  4657.6 1351.90  4687.7 1350.62  4737.9 1350.39  4778.1 1348.83  4817.9 1345.63
  4848.4 1345.31  4878.5 1343.64  4898.6 1342.20  4928.1 1336.20  4938.8 1335.56
  4948.8 1333.05  5004.7 1330.68  5005.2 1330.18  5014.0 1330.68  5040.6 1331.92
  5051.0 1333.95  5057.5 1336.90  5062.7 1337.34  5123.8 1339.67  5348.7 1340.15
  5477.4 1346.81  5499.5 1346.74  5539.8 1344.43  5591.8 1346.29  5654.2 1352.50
  5685.4 1353.02  5751.7 1357.52  5779.0 1361.10  5819.3 1363.61  5841.4 1363.89
#Mann=3,-1,0
  4657.6    0.05       0  5004.7    0.03       0  5014.0    0.05       0
Bank Sta=5004.7,5014
Exp/Cntr=0.3,0.1

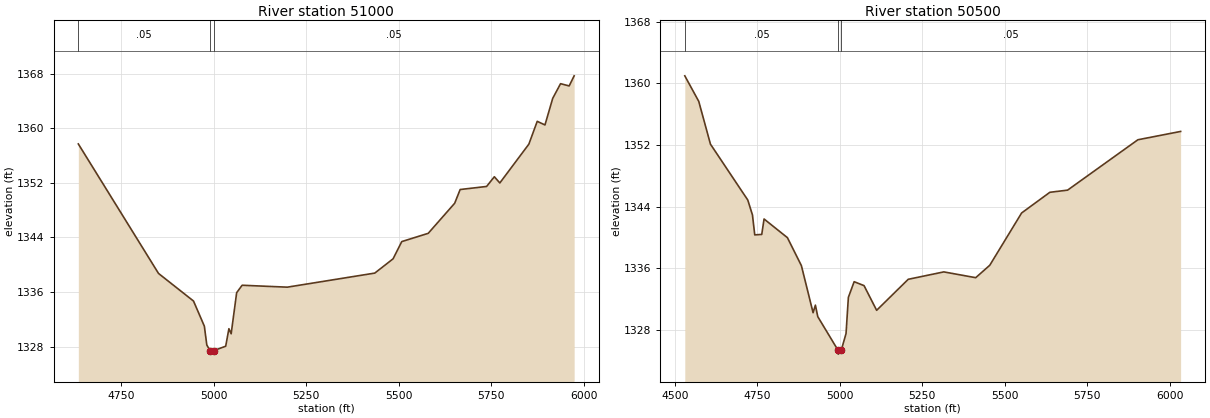
Type RM Length L Ch R = 1,51000,500,500,500
BEGIN DESCRIPTION:
BULLHEAD CREEK 102.0
END DESCRIPTION:
XS GIS Cut Line= 3
      2769655.68     10183353.11      2770009.85     10183264.02
      2770805.65     10182703.13
#Sta/Elev= 30
  4634.8 1357.69  4851.3 1338.74  4945.8 1334.70  4975.1 1331.02  4981.7 1328.27
  4990.6 1327.43  4991.1 1326.93  4999.9 1327.43  5032.7 1328.09  5041.4 1330.65
  5047.5 1329.91  5062.3 1335.92  5077.1 1337.01  5199.0 1336.73  5435.3 1338.79
  5484.7 1340.88  5508.1 1343.40  5579.6 1344.61  5651.0 1349.01  5665.8 1351.02
  5737.2 1351.47  5758.1 1352.89  5772.9 1351.98  5851.3 1357.66  5873.9 1361.00
  5894.8 1360.47  5915.7 1364.36  5936.9 1366.51  5960.1 1366.18  5973.6 1367.66
#Mann=3,-1,0
  4634.8    0.05       0  4990.6    0.05       0  4999.9    0.05       0
Bank Sta=4990.6,4999.9
Exp/Cntr=0.3,0.1

Type RM Length L Ch R = 1,50500,500,500,500
BEGIN DESCRIPTION:
BULLHEAD CREEK 101.0
END DESCRIPTION:
XS GIS Cut Line= 3
      2769605.71     10183403.14      2769941.61     10183732.02
      2770905.66     10184103.10
#Sta/Elev= 30
  4529.9 1360.97  4572.2 1357.66  4607.7 1352.11  4720.8 1344.87  4735.0 1342.94
  4742.0 1340.35  4763.2 1340.41  4770.2 1342.41  4841.0 1339.99  4883.4 1336.36
  4918.8 1330.26  4925.8 1331.24  4933.0 1329.75  4994.5 1325.39  4995.0 1324.89
  5004.2 1325.39  5018.7 1327.56  5025.8 1332.25  5043.3 1334.28  5073.3 1333.77
  5111.5 1330.57  5207.2 1334.59  5315.1 1335.55  5411.8 1334.80  5454.4 1336.41
  5551.0 1343.19  5636.6 1345.87  5690.3 1346.15  5903.4 1352.68  6033.0 1353.76
#Mann=3,-1,0
  4529.9    0.05       0  4994.5    0.03       0  5004.2    0.05       0
Bank Sta=4994.5,5004.2
Exp/Cntr=0.3,0.1