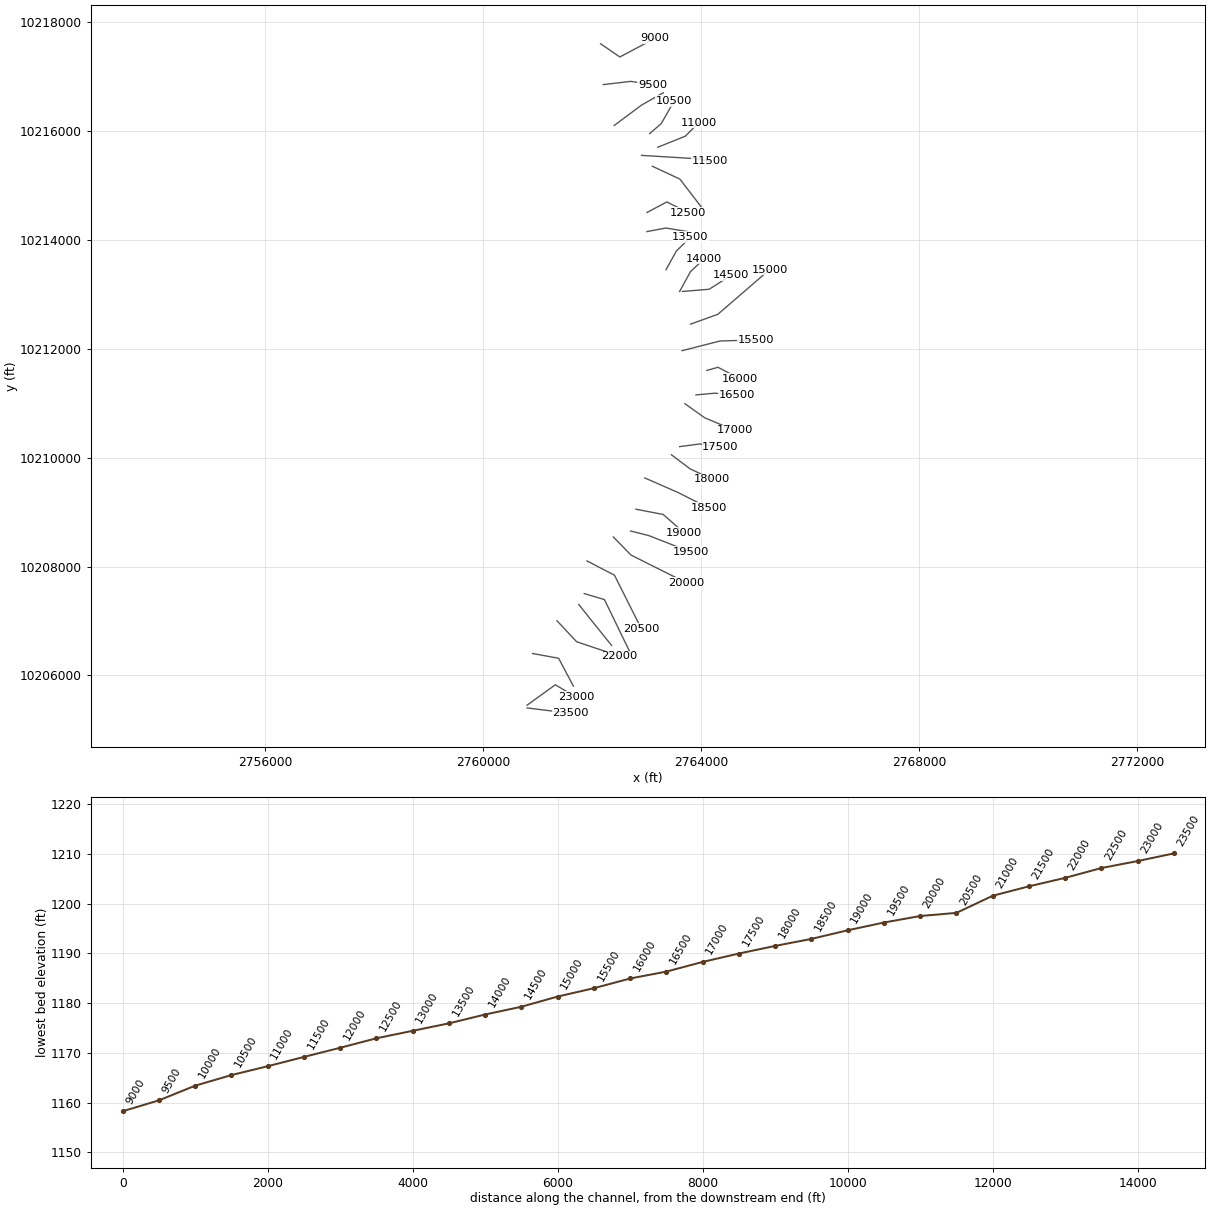
HEC-RAS study BULLHEAD CREEK.prj: BULLHEAD CREEK Base Level Engineering

--- BULLHEAD CREEK.g01 (geometry) --- (continued)

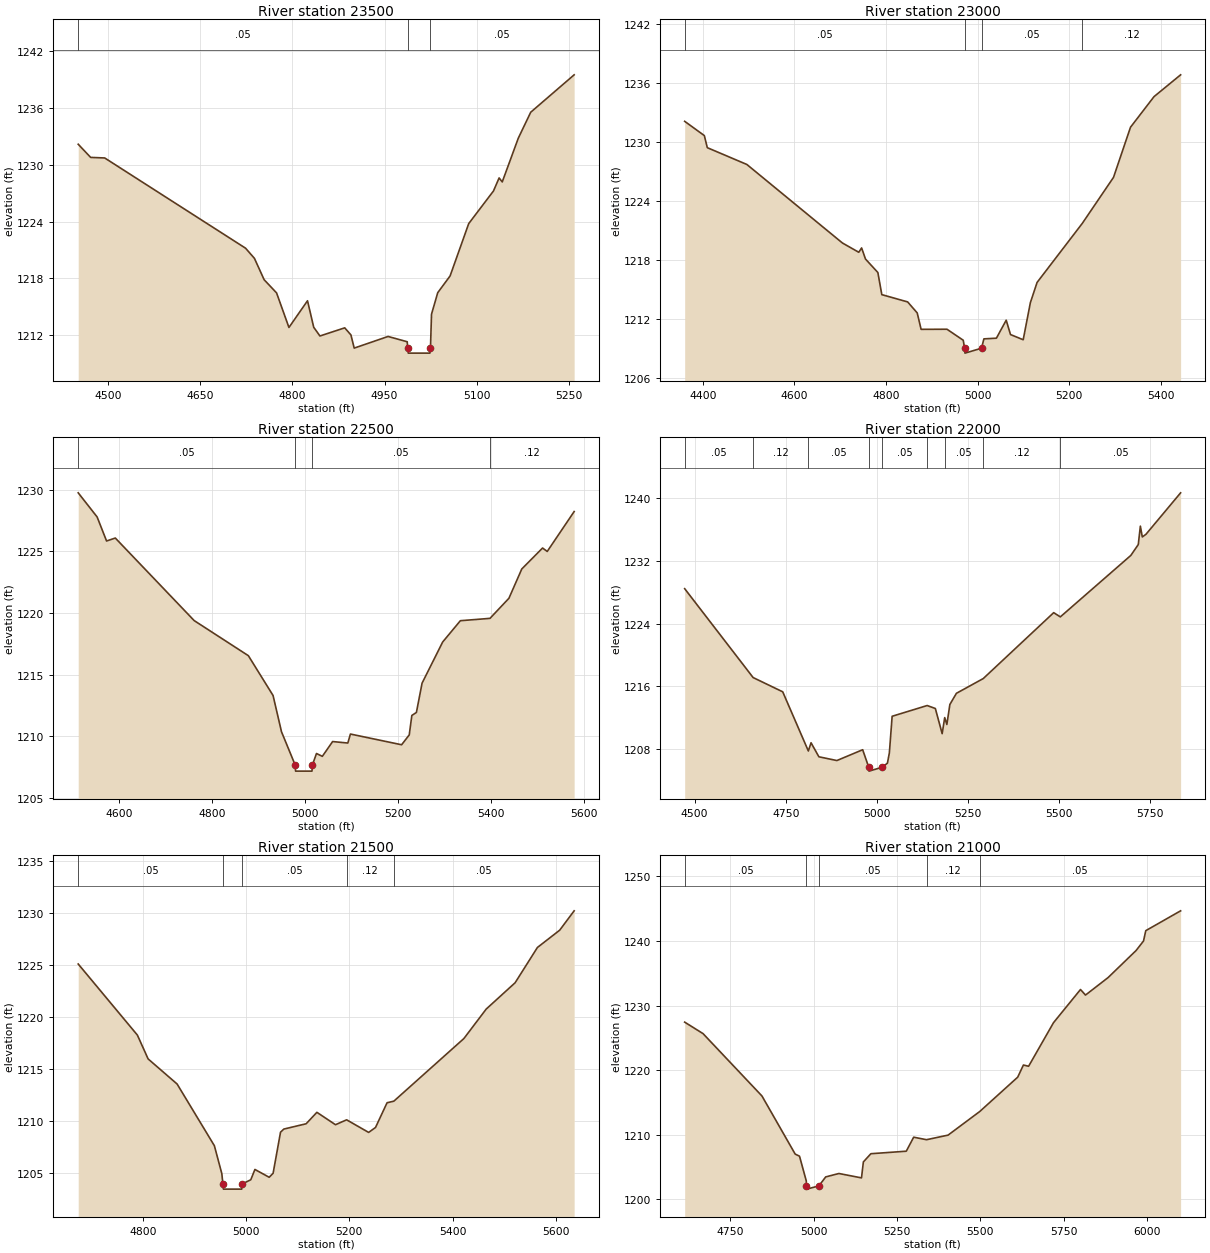
Type RM Length L Ch R = 1,23500,500,500,500
BEGIN DESCRIPTION:
BULLHEAD CREEK 47.0
END DESCRIPTION:
XS GIS Cut Line= 3
      2760805.65     10205403.12      2761349.52     10205335.98
      2761605.72     10205303.11
#Sta/Elev= 30
  4452.0 1232.16  4472.2 1230.77  4495.1 1230.71  4724.1 1221.18  4738.5 1220.11
  4754.3 1217.85  4774.5 1216.46  4794.6 1212.81  4824.8 1215.63  4834.9 1212.83
  4845.0 1211.91  4885.3 1212.77  4895.4 1212.02  4900.7 1210.63  4955.8 1211.86
  4986.9 1211.30  4987.7 1210.60  4988.6 1210.10  5023.8 1210.10  5024.7 1210.60
  5026.4 1214.21  5036.5 1216.48  5056.6 1218.25  5086.9 1223.78  5127.2 1227.23
  5136.3 1228.60  5141.4 1228.18  5167.5 1232.80  5187.7 1235.54  5258.3 1239.49
#Mann=3,-1,0
  4452.0    0.05       0  4987.7    0.03       0  5024.7    0.05       0
Bank Sta=4987.7,5024.7
Exp/Cntr=0.3,0.1

Type RM Length L Ch R = 1,23000,500,500,500
BEGIN DESCRIPTION:
BULLHEAD CREEK 46.0
END DESCRIPTION:
XS GIS Cut Line= 3
      2760805.69     10205453.12      2761323.62     10205828.06
      2761705.72     10205603.09
#Sta/Elev= 30
  4360.6 1232.14  4403.5 1230.69  4410.0 1229.46  4496.4 1227.75  4705.1 1219.76
  4740.7 1218.82  4746.9 1219.26  4755.4 1218.13  4782.4 1216.76  4791.0 1214.51
  4847.4 1213.77  4868.3 1212.65  4876.8 1210.98  4933.3 1210.99  4968.8 1209.87
  4971.7 1209.06  4972.6 1208.56  5008.7 1209.06  5013.9 1210.01  5041.2 1210.08
  5062.6 1211.91  5072.0 1210.45  5099.7 1209.92  5115.4 1213.70  5130.0 1215.75
  5228.6 1221.75  5296.9 1226.44  5334.0 1231.54  5385.3 1234.65  5443.4 1236.87
#Mann=4,-1,0
  4360.6    0.05       0  4971.7    0.03       0  5008.7    0.05       0
  5228.6    0.12       0
Bank Sta=4971.7,5008.7
Exp/Cntr=0.3,0.1

Type RM Length L Ch R = 1,22500,500,500,500
BEGIN DESCRIPTION:
BULLHEAD CREEK 45.0
END DESCRIPTION:
XS GIS Cut Line= 3
      2760905.64     10206403.12      2761385.06     10206315.29
      2761655.69     10205803.09
#Sta/Elev= 30
  4512.6 1229.75  4553.3 1227.79  4573.6 1225.84  4592.4 1226.08  4762.0 1219.38
  4878.6 1216.53  4931.7 1213.30  4949.8 1210.36  4979.2 1207.66  4980.1 1207.16
  5015.4 1207.16  5016.3 1207.66  5025.1 1208.59  5037.7 1208.36  5059.8 1209.56
  5092.5 1209.44  5098.1 1210.17  5208.2 1209.30  5224.6 1210.10  5230.2 1211.68
  5240.0 1211.92  5252.2 1214.30  5296.5 1217.64  5334.6 1219.37  5398.3 1219.56
  5439.0 1221.19  5466.7 1223.57  5511.4 1225.27  5521.4 1224.99  5579.3 1228.23
#Mann=4,-1,0
  4512.6    0.05       0  4979.2    0.03       0  5016.3    0.05       0
  5398.3    0.12       0
Bank Sta=4979.2,5016.3
Exp/Cntr=0.3,0.1

Type RM Length L Ch R = 1,22000,500,500,500
BEGIN DESCRIPTION:
BULLHEAD CREEK 44.0
END DESCRIPTION:
XS GIS Cut Line= 3
      2761355.68     10207003.11      2761716.22     10206618.19
      2762505.70     10206353.11
#Sta/Elev= 30
  4472.6 1228.46  4660.3 1217.12  4741.5 1215.30  4811.8 1207.75  4819.2 1208.80
  4840.7 1207.01  4890.0 1206.53  4960.8 1207.91  4977.4 1205.68  4978.3 1205.18
  5014.6 1205.68  5028.7 1206.20  5034.0 1207.51  5041.6 1212.18  5137.7 1213.55
  5160.1 1213.17  5178.8 1209.96  5185.8 1212.01  5191.7 1211.13  5199.9 1213.68
  5217.9 1215.11  5291.5 1216.99  5484.7 1225.40  5502.9 1224.86  5696.2 1232.70
  5716.7 1234.09  5722.4 1236.44  5727.7 1235.06  5737.8 1235.40  5832.8 1240.69
#Mann=9,-1,0
  4472.6    0.05       0  4660.3    0.12       0  4811.8    0.05       0
  4977.4    0.05       0  5014.6    0.05       0  5137.7    0.12       0
  5185.8    0.05       0  5291.5    0.12       0  5502.9    0.05       0
Bank Sta=4977.4,5014.6
Exp/Cntr=0.3,0.1

Type RM Length L Ch R = 1,21500,500,500,500
BEGIN DESCRIPTION:
BULLHEAD CREEK 43.0
END DESCRIPTION:
XS GIS Cut Line= 3
      2761755.71     10207303.08      2761957.08     10207048.11
      2762355.66     10206553.14
#Sta/Elev= 30
  4675.1 1225.11  4789.7 1218.28  4810.5 1215.99  4866.6 1213.58  4938.8 1207.65
  4953.2 1204.97  4955.3 1203.98  4956.3 1203.48  4991.8 1203.48  4992.7 1203.98
  5009.3 1204.38  5017.3 1205.37  5044.9 1204.62  5052.5 1205.00  5066.9 1208.95
  5073.3 1209.25  5116.5 1209.76  5137.3 1210.86  5173.3 1209.67  5194.9 1210.14
  5237.5 1208.93  5250.8 1209.40  5273.2 1211.78  5286.3 1211.93  5422.0 1217.95
  5465.2 1220.78  5521.2 1223.31  5564.4 1226.70  5607.5 1228.36  5635.5 1230.22
#Mann=5,-1,0
  4675.1    0.05       0  4955.3    0.03       0  4992.7    0.05       0
  5194.9    0.12       0  5286.3    0.05       0
Bank Sta=4955.3,4992.7
Exp/Cntr=0.3,0.1

Type RM Length L Ch R = 1,21000,500,500,500
BEGIN DESCRIPTION:
BULLHEAD CREEK 42.0
END DESCRIPTION:
XS GIS Cut Line= 3
      2761855.67     10207503.11      2762225.92     10207393.26
      2762705.70     10206403.07
#Sta/Elev= 30
  4613.8 1227.43  4668.9 1225.65  4845.4 1216.00  4945.1 1207.00  4958.0 1206.68
  4978.3 1202.85  4978.5 1202.08  4979.5 1201.58  5016.0 1202.08  5036.5 1203.47
  5076.1 1204.00  5143.8 1203.32  5149.4 1205.79  5171.9 1207.06  5278.0 1207.45
  5300.2 1209.62  5338.7 1209.23  5403.3 1209.94  5498.1 1213.59  5612.0 1218.91
  5629.1 1220.79  5644.7 1220.60  5719.4 1227.35  5800.2 1232.48  5815.2 1231.62
  5883.0 1234.33  5966.9 1238.52  5989.1 1239.99  5995.9 1241.59  6100.3 1244.66
#Mann=5,-1,0
  4613.8    0.05       0  4978.5    0.03       0  5016.0    0.05       0
  5338.7    0.12       0  5498.1    0.05       0
Bank Sta=4978.5,5016
Exp/Cntr=0.3,0.1

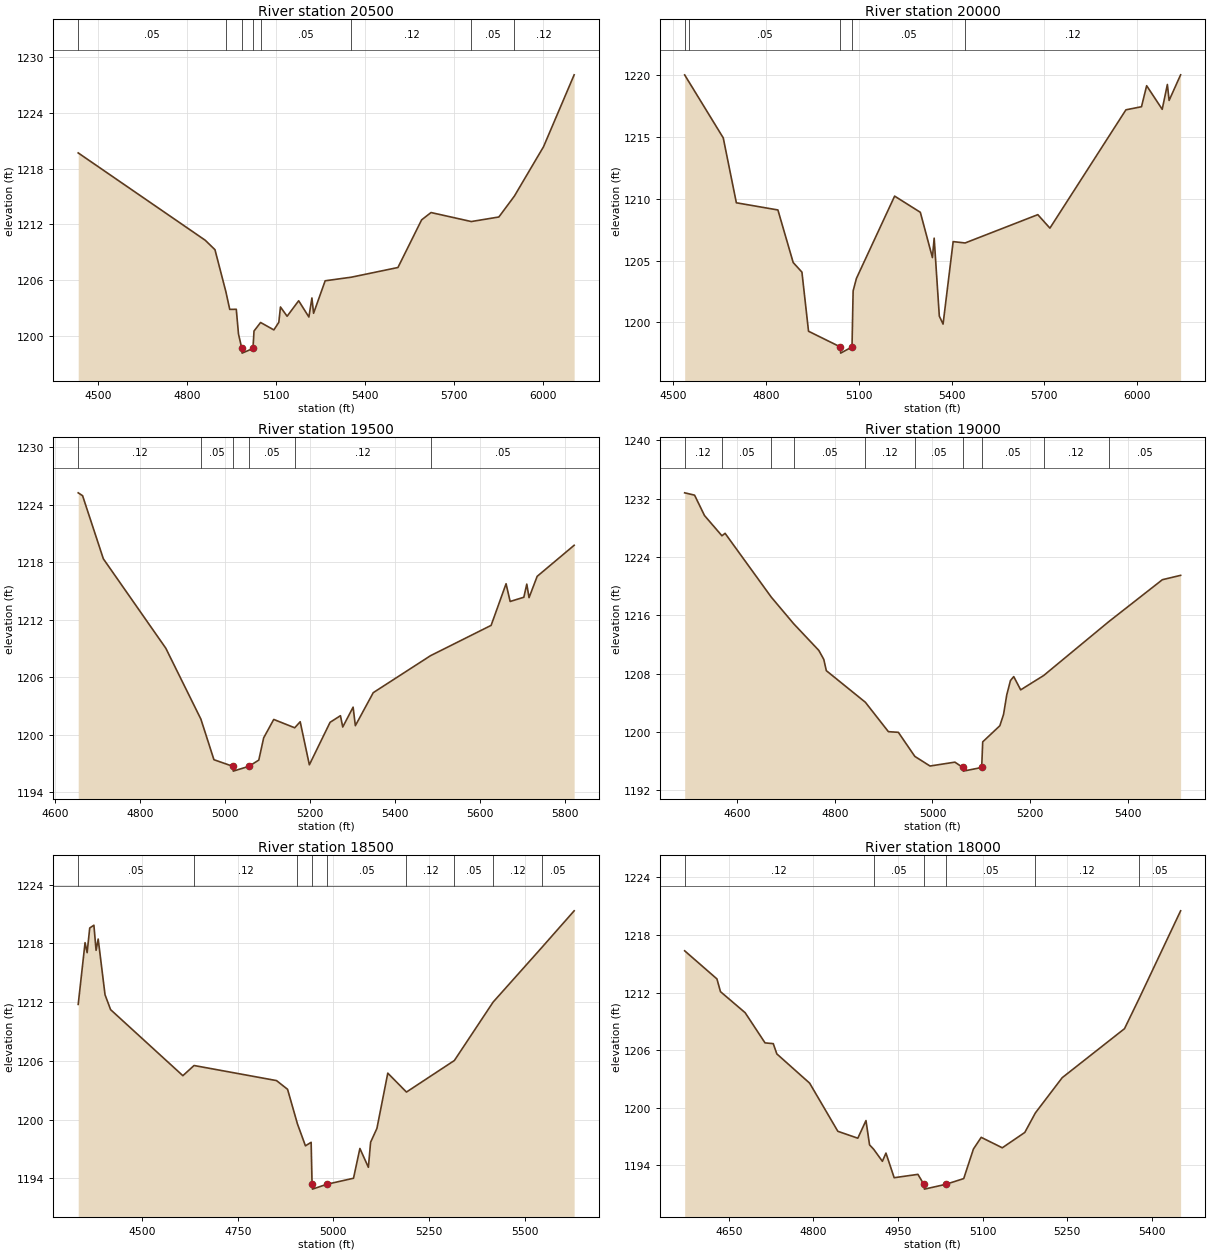
Type RM Length L Ch R = 1,20500,500,500,500
BEGIN DESCRIPTION:
BULLHEAD CREEK 41.0
END DESCRIPTION:
XS GIS Cut Line= 3
      2761905.66     10208103.12      2762409.42     10207841.60
      2762905.70     10206853.08
#Sta/Elev= 30
  4432.4 1219.70  4860.9 1210.30  4893.9 1209.28  4930.7 1204.76  4943.8 1202.85
  4965.9 1202.86  4973.3 1200.20  4984.6 1198.64  4985.5 1198.14  5022.2 1198.64
  5025.7 1200.52  5047.9 1201.44  5092.7 1200.64  5109.4 1201.46  5115.0 1203.11
  5137.4 1202.11  5176.4 1203.78  5210.9 1202.03  5221.1 1204.08  5226.7 1202.43
  5265.8 1205.93  5354.6 1206.32  5511.4 1207.36  5591.3 1212.49  5623.1 1213.28
  5759.0 1212.31  5852.0 1212.80  5904.4 1215.05  6002.8 1220.37  6106.1 1228.11
#Mann=8,-1,0
  4432.4    0.05       0  4930.7    0.12       0  4984.6    0.07       0
  5022.2    0.12       0  5047.9    0.05       0  5354.6    0.12       0
  5759.0    0.05       0  5904.4    0.12       0
Bank Sta=4984.6,5022.2
Exp/Cntr=0.3,0.1

Type RM Length L Ch R = 1,20000,500,500,500
BEGIN DESCRIPTION:
BULLHEAD CREEK 40.0
END DESCRIPTION:
XS GIS Cut Line= 3
      2762390.01     10208543.62      2762712.50     10208211.82
      2763732.24     10207700.62
#Sta/Elev= 30
  4537.3 1220.01  4550.1 1219.49  4662.0 1214.92  4704.4 1209.67  4838.7 1209.09
  4888.1 1204.84  4916.4 1204.06  4937.7 1199.28  5040.6 1198.01  5041.6 1197.51
  5078.3 1198.01  5081.9 1202.54  5092.5 1203.55  5216.1 1210.21  5299.2 1208.90
  5338.3 1205.24  5343.9 1206.81  5360.6 1200.50  5372.7 1199.86  5405.3 1206.53
  5443.9 1206.42  5679.0 1208.71  5718.1 1207.62  5963.9 1217.19  6014.2 1217.44
  6030.9 1219.14  6081.2 1217.23  6097.9 1219.24  6103.5 1217.95  6140.7 1220.02
#Mann=5,-1,0
  4537.3    0.12       0  4550.1    0.05       0  5040.6    0.03       0
  5078.3    0.05       0  5443.9    0.12       0
Bank Sta=5040.6,5078.3
Exp/Cntr=0.3,0.1

Type RM Length L Ch R = 1,19500,500,500,500
BEGIN DESCRIPTION:
BULLHEAD CREEK 39.0
END DESCRIPTION:
XS GIS Cut Line= 3
      2762705.68     10208653.11      2763040.88     10208568.94
      2763805.96     10208267.85
#Sta/Elev= 30
  4654.4 1225.22  4664.7 1224.92  4713.6 1218.34  4860.6 1209.02  4943.3 1201.62
  4974.0 1197.39  5018.6 1196.70  5019.5 1196.20  5056.3 1196.70  5079.6 1197.35
  5091.1 1199.67  5114.8 1201.59  5164.2 1200.72  5177.1 1201.35  5198.7 1196.86
  5247.5 1201.29  5271.9 1201.98  5277.3 1200.80  5301.7 1202.87  5307.0 1200.94
  5349.1 1204.38  5484.1 1208.24  5626.7 1211.40  5661.9 1215.74  5671.5 1213.89
  5703.7 1214.33  5710.7 1215.70  5716.0 1214.29  5735.1 1216.51  5822.2 1219.75
#Mann=6,-1,0
  4654.4    0.12       0  4943.3    0.05       0  5018.6    0.03       0
  5056.3    0.05       0  5164.2    0.12       0  5484.1    0.05       0
Bank Sta=5018.6,5056.3
Exp/Cntr=0.3,0.1

Type RM Length L Ch R = 1,19000,500,500,500
BEGIN DESCRIPTION:
BULLHEAD CREEK 38.0
END DESCRIPTION:
XS GIS Cut Line= 3
      2762805.73     10209053.10      2763304.34     10208956.93
      2763686.87     10208621.75
#Sta/Elev= 30
  4492.2 1232.79  4512.5 1232.47  4532.9 1229.67  4568.6 1226.90  4575.0 1227.24
  4669.7 1218.49  4715.5 1214.85  4767.1 1211.19  4777.3 1209.96  4782.5 1208.41
  4862.5 1204.08  4909.7 1200.05  4930.1 1199.96  4963.9 1196.66  4995.0 1195.34
  5046.0 1195.87  5062.2 1195.14  5063.2 1194.64  5100.9 1195.14  5103.0 1198.65
  5138.1 1200.86  5145.7 1202.41  5152.3 1205.10  5159.9 1207.06  5166.6 1207.60
  5180.8 1205.78  5228.0 1207.75  5361.0 1215.11  5471.2 1220.88  5508.6 1221.48
#Mann=10,-1,0
  4492.2    0.12       0  4568.6    0.05       0  4669.7    0.12       0
  4715.5    0.05       0  4862.5    0.12       0  4963.9    0.05       0
  5062.2    0.03       0  5100.9    0.05       0  5228.0    0.12       0
  5361.0    0.05       0
Bank Sta=5062.2,5100.9
Exp/Cntr=0.3,0.1

Type RM Length L Ch R = 1,18500,500,500,500
BEGIN DESCRIPTION:
BULLHEAD CREEK 37.0
END DESCRIPTION:
XS GIS Cut Line= 3
      2762968.11     10209626.95      2763578.89     10209359.43
      2764140.05     10209074.84
#Sta/Elev= 30
  4333.2 1211.77  4351.1 1218.07  4356.5 1217.05  4363.3 1219.57  4374.2 1219.85
  4379.9 1217.29  4385.4 1218.44  4403.3 1212.75  4417.9 1211.23  4606.7 1204.49
  4635.9 1205.53  4851.4 1203.99  4880.3 1203.10  4906.2 1199.56  4927.0 1197.33
  4941.9 1197.69  4944.3 1193.41  4945.3 1192.91  4983.2 1193.41  5052.6 1194.02
  5069.3 1197.06  5091.5 1195.14  5097.3 1197.70  5113.8 1199.11  5142.2 1204.75
  5191.0 1202.82  5316.2 1206.04  5417.4 1212.00  5544.8 1217.58  5629.2 1221.32
#Mann=9,-1,0
  4333.2    0.05       0  4635.9    0.12       0  4906.2    0.05       0
  4944.3    0.03       0  4983.2    0.05       0  5191.0    0.12       0
  5316.2    0.05       0  5417.4    0.12       0  5544.8    0.05       0
Bank Sta=4944.3,4983.2
Exp/Cntr=0.3,0.1

Type RM Length L Ch R = 1,18000,500,500,500
BEGIN DESCRIPTION:
BULLHEAD CREEK 36.0
END DESCRIPTION:
XS GIS Cut Line= 3
      2763455.71     10210053.09      2763797.45     10209794.92
      2764205.73     10209603.09
#Sta/Elev= 30
  4571.7 1216.35  4628.9 1213.42  4635.2 1212.09  4678.9 1209.90  4714.2 1206.75
  4728.8 1206.67  4735.1 1205.60  4793.3 1202.55  4843.3 1197.53  4878.7 1196.81
  4893.2 1198.65  4899.5 1196.12  4906.8 1195.66  4922.3 1194.40  4928.6 1195.26
  4943.2 1192.69  4985.3 1193.04  4995.8 1192.00  4996.8 1191.50  5034.8 1192.00
  5066.5 1192.60  5083.7 1195.68  5097.5 1196.90  5134.9 1195.81  5174.8 1197.41
  5193.6 1199.45  5241.1 1203.12  5351.6 1208.23  5377.9 1211.42  5451.1 1220.52
#Mann=6,-1,0
  4571.7    0.12       0  4906.8    0.05       0  4995.8    0.03       0
  5034.8    0.05       0  5193.6    0.12       0  5377.9    0.05       0
Bank Sta=4995.8,5034.8
Exp/Cntr=0.3,0.1

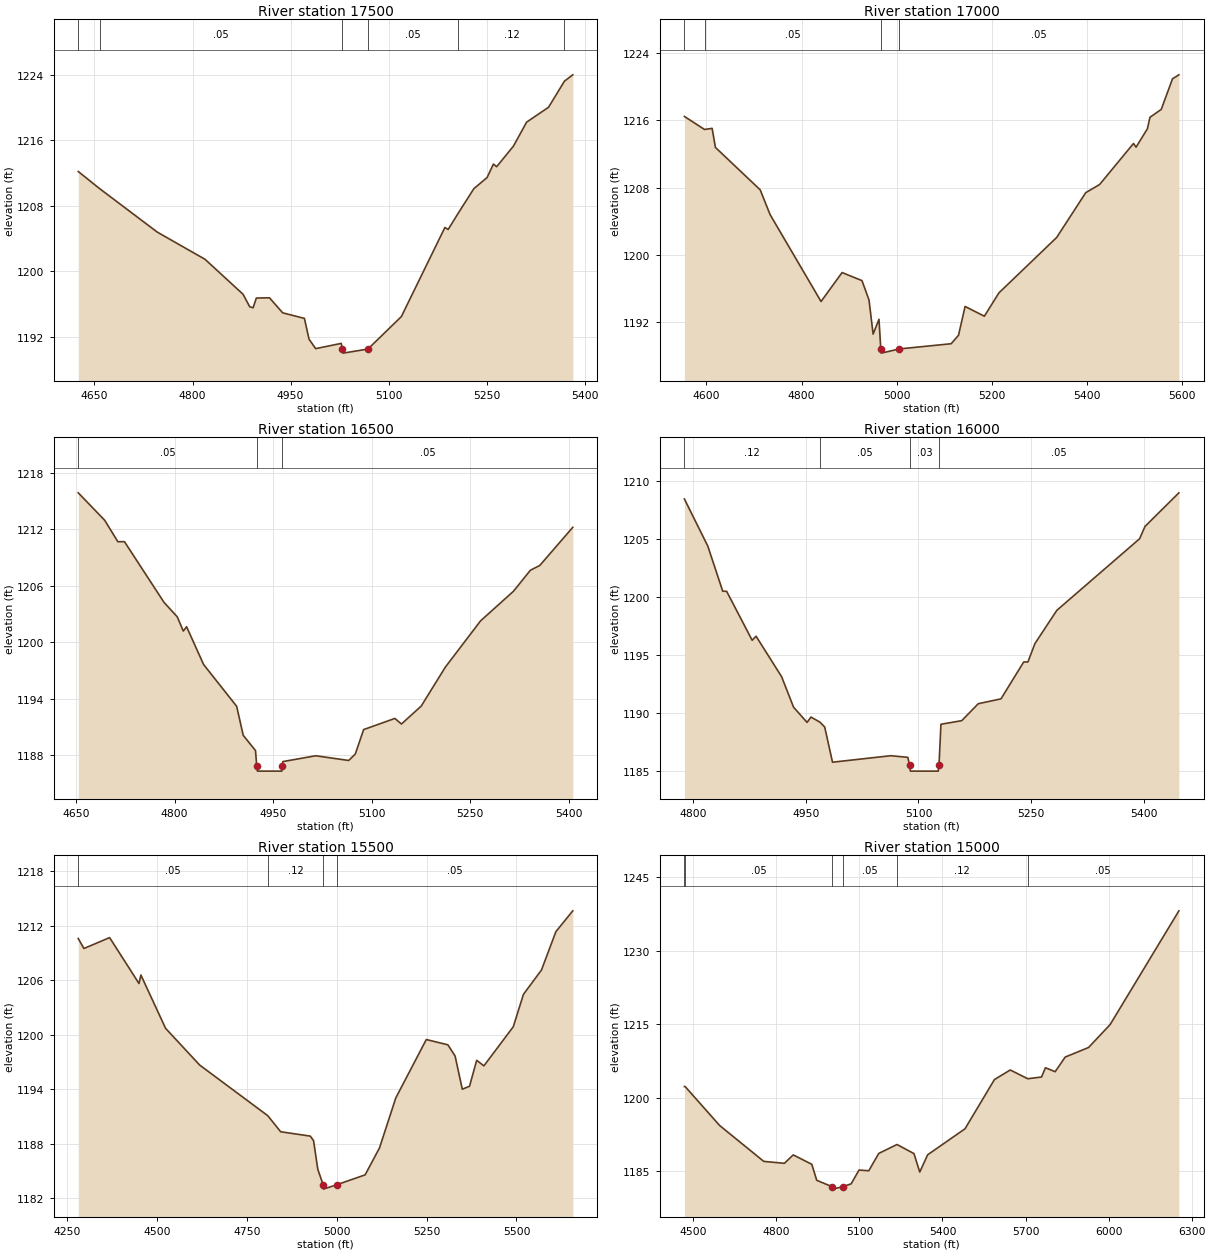
Type RM Length L Ch R = 1,17500,500,500,500
BEGIN DESCRIPTION:
BULLHEAD CREEK 35.0
END DESCRIPTION:
XS GIS Cut Line= 3
      2763605.71     10210203.12      2763977.29     10210252.16
      2764355.72     10210203.11
#Sta/Elev= 30
  4625.2 1212.19  4657.8 1210.10  4746.2 1204.77  4819.1 1201.45  4877.3 1197.17
  4887.4 1195.65  4892.6 1195.52  4897.6 1196.71  4917.7 1196.74  4937.9 1194.90
  4971.1 1194.22  4978.2 1191.68  4988.3 1190.52  5027.5 1191.16  5029.3 1190.47
  5030.3 1189.97  5068.3 1190.47  5119.4 1194.44  5186.0 1205.34  5191.0 1205.10
  5206.7 1207.13  5230.3 1210.09  5250.5 1211.45  5260.2 1213.10  5265.2 1212.78
  5290.8 1215.29  5311.0 1218.23  5344.5 1220.05  5368.9 1223.25  5381.6 1224.02
#Mann=6,-1,0
  4625.2    0.12       0  4657.8    0.05       0  5029.3    0.03       0
  5068.3    0.05       0  5206.7    0.12       0  5368.9    0.05       0
Bank Sta=5029.3,5068.3
Exp/Cntr=0.3,0.1

Type RM Length L Ch R = 1,17000,500,500,500
BEGIN DESCRIPTION:
BULLHEAD CREEK 34.0
END DESCRIPTION:
XS GIS Cut Line= 3
      2763702.55     10210991.50      2764066.24     10210732.81
      2764612.31     10210502.64
#Sta/Elev= 30
  4553.7 1216.48  4596.0 1214.93  4612.0 1215.06  4618.9 1212.79  4712.9 1207.74
  4733.8 1204.78  4840.8 1194.43  4885.0 1197.88  4926.8 1196.92  4941.6 1194.60
  4950.2 1190.55  4962.5 1192.31  4966.3 1188.78  4967.3 1188.28  5005.4 1188.78
  5114.2 1189.40  5129.6 1190.41  5143.4 1193.84  5183.9 1192.68  5214.5 1195.46
  5335.8 1202.06  5396.9 1207.40  5426.0 1208.37  5497.2 1213.26  5502.6 1212.82
  5526.4 1215.01  5531.8 1216.38  5555.5 1217.32  5579.2 1220.97  5592.6 1221.44
#Mann=4,-1,0
  4553.7    0.12       0  4596.0    0.05       0  4966.3    0.03       0
  5005.4    0.05       0
Bank Sta=4966.3,5005.4
Exp/Cntr=0.3,0.1

Type RM Length L Ch R = 1,16500,500,500,500
BEGIN DESCRIPTION:
BULLHEAD CREEK 33.0
END DESCRIPTION:
XS GIS Cut Line= 3
      2763905.64     10211153.11      2764250.69     10211184.79
      2764655.66     10211153.11
#Sta/Elev= 30
  4653.5 1215.87  4693.7 1212.96  4713.8 1210.68  4723.8 1210.69  4784.1 1204.24
  4804.2 1202.71  4813.4 1201.20  4818.4 1201.66  4844.3 1197.65  4894.6 1193.22
  4904.6 1190.14  4923.3 1188.52  4925.2 1186.84  4926.2 1186.34  4963.3 1186.34
  4964.3 1186.84  4964.8 1187.35  5015.0 1187.97  5065.2 1187.47  5075.2 1188.16
  5087.9 1190.75  5135.4 1191.93  5145.4 1191.34  5175.5 1193.24  5212.3 1197.38
  5265.8 1202.28  5316.0 1205.43  5341.6 1207.65  5356.1 1208.17  5406.2 1212.21
#Mann=3,-1,0
  4653.5    0.05       0  4925.2    0.03       0  4964.3    0.05       0
Bank Sta=4925.2,4964.3
Exp/Cntr=0.3,0.1

Type RM Length L Ch R = 1,16000,500,500,500
BEGIN DESCRIPTION:
BULLHEAD CREEK 32.0
END DESCRIPTION:
XS GIS Cut Line= 3
      2764105.67     10211603.11      2764309.64     10211660.54
      2764705.70     10211453.10
#Sta/Elev= 30
  4788.1 1208.41  4819.3 1204.35  4839.2 1200.46  4844.4 1200.45  4878.4 1196.23
  4883.6 1196.58  4917.6 1193.10  4933.6 1190.46  4951.6 1189.15  4956.8 1189.61
  4968.8 1189.17  4975.1 1188.75  4985.5 1185.72  5063.3 1186.28  5085.8 1186.14
  5088.3 1185.45  5089.3 1184.95  5126.4 1184.95  5127.4 1185.45  5130.0 1188.99
  5157.7 1189.30  5179.7 1190.76  5210.0 1191.18  5240.3 1194.36  5245.9 1194.36
  5255.2 1195.94  5284.4 1198.81  5394.7 1204.98  5401.9 1206.04  5447.1 1208.94
#Mann=4,-1,0
  4788.1    0.12       0  4968.8    0.05       0  5088.3    0.03       0
  5127.4    0.05       0
Bank Sta=5088.3,5127.4
Exp/Cntr=0.3,0.1

Type RM Length L Ch R = 1,15500,500,500,500
BEGIN DESCRIPTION:
BULLHEAD CREEK 31.0
END DESCRIPTION:
XS GIS Cut Line= 3
      2763650.48     10211965.49      2764346.50     10212143.01
      2765002.69     10212163.33
#Sta/Elev= 30
  4281.7 1210.61  4297.4 1209.51  4368.9 1210.71  4450.6 1205.65  4455.8 1206.59
  4524.4 1200.72  4619.2 1196.67  4808.6 1191.09  4844.4 1189.32  4926.9 1188.84
  4935.9 1188.34  4947.6 1185.19  4962.4 1183.50  4963.4 1183.00  5001.5 1183.50
  5079.2 1184.57  5119.2 1187.54  5164.5 1193.05  5249.3 1199.48  5309.3 1198.90
  5329.3 1197.67  5349.4 1194.01  5369.4 1194.33  5389.4 1197.19  5409.4 1196.58
  5491.1 1200.89  5519.4 1204.46  5569.5 1207.14  5609.5 1211.36  5656.5 1213.66
#Mann=4,-1,0
  4281.7    0.05       0  4808.6    0.12       0  4962.4    0.03       0
  5001.5    0.05       0
Bank Sta=4962.4,5001.5
Exp/Cntr=0.3,0.1

Type RM Length L Ch R = 1,15000,500,500,500
BEGIN DESCRIPTION:
BULLHEAD CREEK 30.0
END DESCRIPTION:
XS GIS Cut Line= 3
      2763805.71     10212453.12      2764306.75     10212633.15
      2765255.67     10213453.10
#Sta/Elev= 30
  4467.6 1202.27  4470.4 1202.26  4595.1 1194.30  4754.5 1186.98  4828.9 1186.59
  4860.7 1188.31  4927.9 1186.39  4945.7 1183.12  5001.1 1181.82  5002.1 1181.32
  5040.2 1181.82  5070.0 1182.40  5098.5 1185.21  5133.7 1185.07  5169.8 1188.61
  5235.7 1190.43  5297.1 1188.57  5317.9 1184.81  5346.4 1188.33  5481.4 1193.64
  5587.7 1203.69  5644.8 1205.65  5707.9 1203.86  5757.8 1204.21  5772.0 1206.10
  5807.1 1205.30  5843.3 1208.28  5927.8 1210.24  6005.7 1214.92  6254.1 1238.14
#Mann=6,-1,0
  4467.6    0.12       0  4470.4    0.05       0  5001.1    0.03       0
  5040.2    0.05       0  5235.7    0.12       0  5707.9    0.05       0
Bank Sta=5001.1,5040.2
Exp/Cntr=0.3,0.1

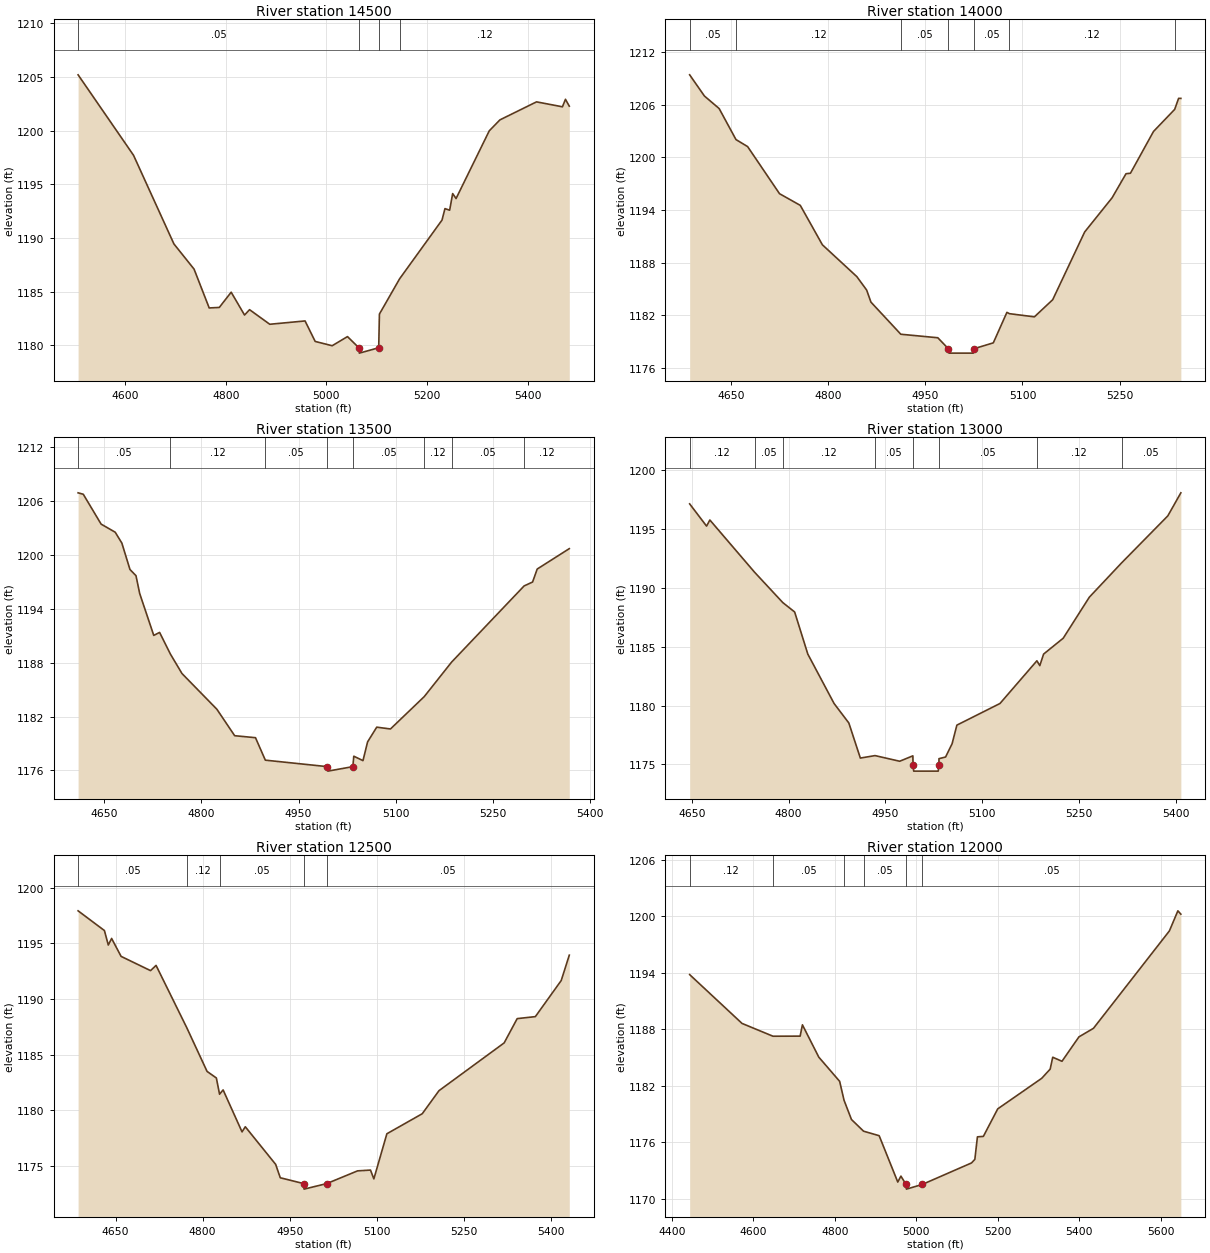
Type RM Length L Ch R = 1,14500,500,500,500
BEGIN DESCRIPTION:
BULLHEAD CREEK 29.0
END DESCRIPTION:
XS GIS Cut Line= 3
      2763655.73     10213053.12      2764148.05     10213093.88
      2764555.70     10213353.12
#Sta/Elev= 30
  4506.0 1205.21  4616.3 1197.71  4696.6 1189.45  4736.7 1187.10  4766.8 1183.48
  4786.9 1183.53  4810.5 1184.95  4837.1 1182.82  4847.1 1183.32  4887.3 1181.96
  4957.5 1182.27  4977.6 1180.36  5011.4 1179.96  5041.9 1180.81  5064.5 1179.77
  5065.5 1179.27  5104.0 1179.77  5105.4 1182.91  5145.6 1186.20  5229.9 1191.67
  5235.8 1192.74  5245.1 1192.59  5251.1 1194.14  5257.9 1193.68  5323.9 1199.99
  5345.1 1201.01  5417.9 1202.69  5469.5 1202.23  5475.5 1202.93  5483.1 1202.29
#Mann=4,-1,0
  4506.0    0.05       0  5064.5    0.03       0  5104.0    0.05       0
  5145.6    0.12       0
Bank Sta=5064.5,5104
Exp/Cntr=0.3,0.1

Type RM Length L Ch R = 1,14000,500,500,500
BEGIN DESCRIPTION:
BULLHEAD CREEK 28.0
END DESCRIPTION:
XS GIS Cut Line= 3
      2763605.68     10213053.11      2763804.73     10213416.68
      2764055.70     10213653.12
#Sta/Elev= 30
  4585.5 1209.39  4608.3 1206.98  4631.1 1205.55  4657.1 1202.02  4675.1 1201.22
  4724.4 1195.86  4756.5 1194.53  4790.7 1190.04  4843.9 1186.42  4859.1 1184.89
  4865.7 1183.52  4911.9 1179.86  4969.1 1179.46  4985.4 1178.21  4986.4 1177.71
  5023.9 1177.71  5024.9 1178.21  5054.9 1178.88  5075.9 1182.35  5079.9 1182.20
  5118.4 1181.84  5146.7 1183.79  5196.1 1191.50  5238.6 1195.40  5260.0 1198.13
  5266.9 1198.19  5302.5 1202.94  5335.3 1205.46  5341.3 1206.71  5344.8 1206.71
#Mann=7,-1,0
  4585.5    0.05       0  4657.1    0.12       0  4911.9    0.05       0
  4985.4    0.05       0  5024.9    0.05       0  5079.9    0.12       0
  5335.3    0.05       0
Bank Sta=4985.4,5024.9
Exp/Cntr=0.3,0.1

Type RM Length L Ch R = 1,13500,500,500,500
BEGIN DESCRIPTION:
BULLHEAD CREEK 27.0
END DESCRIPTION:
XS GIS Cut Line= 3
      2763355.69     10213453.13      2763544.71     10213794.26
      2763805.70     10214053.13
#Sta/Elev= 30
  4610.0 1206.89  4618.0 1206.73  4645.5 1203.41  4667.2 1202.51  4677.5 1201.30
  4690.0 1198.36  4699.3 1197.67  4705.0 1195.69  4726.7 1191.03  4735.7 1191.36
  4752.4 1188.95  4770.2 1186.79  4824.1 1182.81  4851.5 1179.87  4883.6 1179.65
  4898.8 1177.15  4994.3 1176.43  4995.3 1175.93  5033.8 1176.43  5035.2 1177.59
  5049.4 1177.10  5056.5 1179.18  5070.6 1180.82  5091.8 1180.62  5143.9 1184.22
  5186.1 1188.06  5297.9 1196.53  5311.0 1196.97  5318.1 1198.41  5367.6 1200.68
#Mann=8,-1,0
  4610.0    0.05       0  4752.4    0.12       0  4898.8    0.05       0
  4994.3    0.03       0  5033.8    0.05       0  5143.9    0.12       0
  5186.1    0.05       0  5297.9    0.12       0
Bank Sta=4994.3,5033.8
Exp/Cntr=0.3,0.1

Type RM Length L Ch R = 1,13000,500,500,500
BEGIN DESCRIPTION:
BULLHEAD CREEK 26.0
END DESCRIPTION:
XS GIS Cut Line= 3
      2763005.73     10214153.12      2763352.88     10214218.19
      2763755.66     10214153.12
#Sta/Elev= 30
  4646.8 1197.15  4673.0 1195.26  4678.1 1195.78  4747.4 1191.34  4791.1 1188.76
  4809.5 1187.96  4829.9 1184.38  4870.6 1180.18  4893.5 1178.52  4911.3 1175.54
  4934.1 1175.75  4972.3 1175.27  4992.7 1175.73  4993.0 1174.93  4994.0 1174.43
  5032.0 1174.43  5033.0 1174.93  5033.2 1175.49  5043.4 1175.63  5053.5 1176.76
  5060.9 1178.34  5127.7 1180.18  5184.9 1183.81  5189.4 1183.40  5195.3 1184.38
  5225.7 1185.73  5266.2 1189.22  5316.1 1192.13  5387.8 1196.13  5408.0 1198.09
#Mann=8,-1,0
  4646.8    0.12       0  4747.4    0.05       0  4791.1    0.12       0
  4934.1    0.05       0  4993.0    0.03       0  5033.0    0.05       0
  5184.9    0.12       0  5316.1    0.05       0
Bank Sta=4993,5033
Exp/Cntr=0.3,0.1

Type RM Length L Ch R = 1,12500,500,500,500
BEGIN DESCRIPTION:
BULLHEAD CREEK 25.0
END DESCRIPTION:
XS GIS Cut Line= 3
      2763005.71     10214503.12      2763371.26     10214698.31
      2763755.64     10214503.13
#Sta/Elev= 30
  4585.6 1197.92  4630.9 1196.15  4637.6 1194.85  4643.3 1195.44  4659.6 1193.83
  4710.3 1192.55  4719.8 1193.02  4772.9 1187.40  4807.6 1183.50  4823.6 1182.91
  4829.1 1181.45  4835.2 1181.84  4867.8 1178.07  4873.4 1178.53  4925.7 1175.15
  4933.6 1173.95  4973.6 1173.43  4974.6 1172.93  5013.7 1173.43  5066.7 1174.57
  5088.9 1174.64  5094.7 1173.85  5117.1 1177.90  5178.0 1179.70  5206.8 1181.77
  5319.0 1186.06  5341.4 1188.24  5372.7 1188.42  5417.2 1191.66  5431.1 1193.94
#Mann=5,-1,0
  4585.6    0.05       0  4772.9    0.12       0  4829.1    0.05       0
  4973.6    0.03       0  5013.7    0.05       0
Bank Sta=4973.6,5013.7
Exp/Cntr=0.3,0.1

Type RM Length L Ch R = 1,12000,500,500,500
BEGIN DESCRIPTION:
BULLHEAD CREEK 24.0
END DESCRIPTION:
XS GIS Cut Line= 3
      2763105.67     10215353.12      2763609.77     10215118.09
      2764005.70     10214603.09
#Sta/Elev= 30
  4443.8 1193.79  4572.3 1188.61  4648.3 1187.25  4715.0 1187.26  4720.6 1188.46
  4760.8 1185.03  4812.0 1182.46  4822.8 1180.45  4841.0 1178.41  4870.7 1177.17
  4909.0 1176.69  4954.7 1171.77  4962.4 1172.40  4974.9 1171.52  4975.9 1171.02
  5015.0 1171.52  5135.7 1173.80  5143.9 1174.18  5150.2 1176.57  5164.8 1176.62
  5200.1 1179.54  5308.0 1182.78  5328.8 1183.76  5335.1 1185.02  5357.8 1184.59
  5399.4 1187.18  5435.1 1188.09  5621.5 1198.43  5642.3 1200.56  5649.6 1200.21
#Mann=6,-1,0
  4443.8    0.12       0  4648.3    0.05       0  4822.8    0.12       0
  4870.7    0.05       0  4974.9    0.03       0  5015.0    0.05       0
Bank Sta=4974.9,5015
Exp/Cntr=0.3,0.1

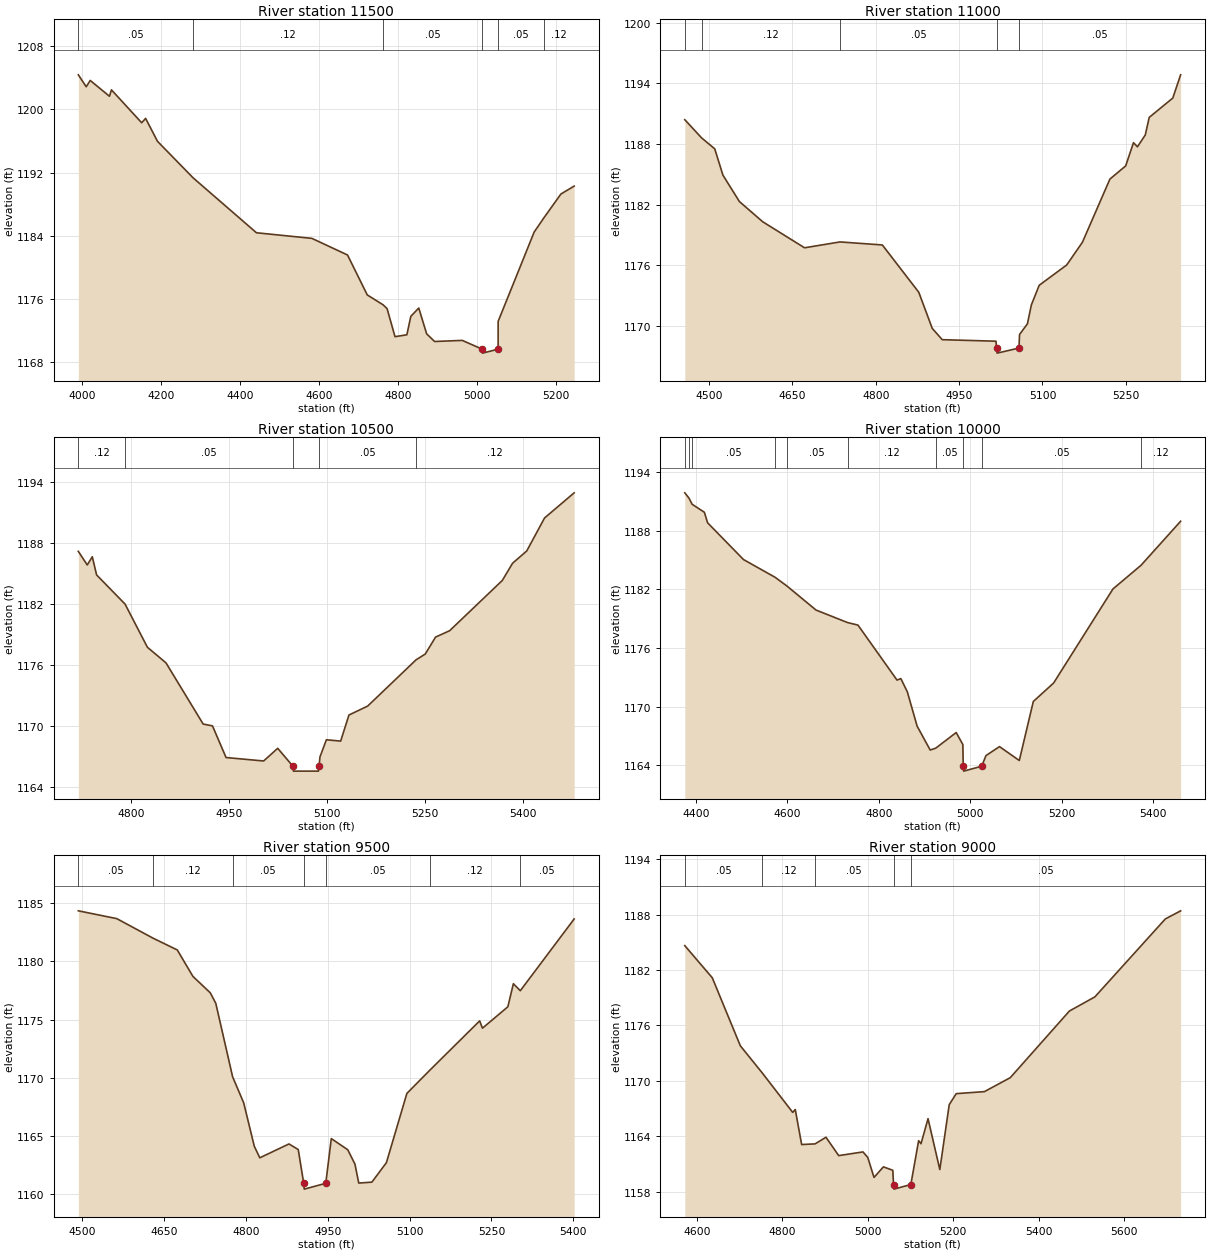
Type RM Length L Ch R = 1,11500,500,500,500
BEGIN DESCRIPTION:
BULLHEAD CREEK 23.0
END DESCRIPTION:
XS GIS Cut Line= 3
      2762905.69     10215553.11      2763912.73     10215491.92
      2764155.65     10215453.12
#Sta/Elev= 30
  3991.1 1204.37  4011.1 1202.86  4021.2 1203.66  4069.9 1201.66  4074.9 1202.47
  4151.4 1198.31  4161.4 1198.86  4191.5 1195.96  4281.7 1191.34  4441.9 1184.40
  4582.2 1183.69  4672.4 1181.59  4722.4 1176.54  4762.4 1175.29  4772.5 1174.81
  4792.6 1171.26  4822.6 1171.50  4832.6 1173.83  4852.7 1174.88  4872.7 1171.62
  4892.8 1170.65  4962.9 1170.79  5013.2 1169.68  5014.2 1169.18  5053.5 1169.68
  5053.6 1173.19  5144.8 1184.49  5170.0 1186.33  5212.5 1189.30  5246.0 1190.30
#Mann=6,-1,0
  3991.1    0.05       0  4281.7    0.12       0  4762.4    0.05       0
  5013.2    0.03       0  5053.5    0.05       0  5170.0    0.12       0
Bank Sta=5013.2,5053.5
Exp/Cntr=0.3,0.1

Type RM Length L Ch R = 1,11000,500,500,500
BEGIN DESCRIPTION:
BULLHEAD CREEK 22.0
END DESCRIPTION:
XS GIS Cut Line= 3
      2763205.67     10215703.11      2763710.33     10215905.42
      2763955.65     10216153.08
#Sta/Elev= 30
  4456.3 1190.40  4486.4 1188.61  4510.2 1187.52  4524.9 1184.92  4554.5 1182.31
  4596.4 1180.31  4671.8 1177.73  4735.7 1178.31  4811.8 1178.01  4877.4 1173.33
  4901.6 1169.76  4919.6 1168.64  5016.3 1168.49  5017.4 1167.81  5018.4 1167.31
  5057.7 1167.81  5058.7 1169.15  5072.9 1170.21  5080.0 1172.08  5094.1 1174.02
  5143.6 1176.03  5171.9 1178.28  5221.4 1184.53  5249.7 1185.83  5263.8 1188.13
  5270.9 1187.72  5285.0 1188.89  5292.1 1190.63  5334.5 1192.54  5348.6 1194.84
#Mann=5,-1,0
  4456.3    0.05       0  4486.4    0.12       0  4735.7    0.05       0
  5017.4    0.03       0  5057.7    0.05       0
Bank Sta=5017.4,5057.7
Exp/Cntr=0.3,0.1

Type RM Length L Ch R = 1,10500,500,500,500
BEGIN DESCRIPTION:
BULLHEAD CREEK 21.0
END DESCRIPTION:
XS GIS Cut Line= 3
      2763055.68     10215953.11      2763268.48     10216137.09
      2763505.69     10216553.11
#Sta/Elev= 30
  4718.7 1187.19  4732.4 1185.85  4740.1 1186.66  4746.7 1184.87  4790.4 1181.99
  4824.6 1177.74  4853.1 1176.20  4910.1 1170.17  4924.4 1169.99  4945.2 1166.87
  5002.8 1166.53  5024.4 1167.78  5047.5 1166.03  5048.5 1165.53  5086.8 1165.53
  5087.8 1166.03  5089.2 1166.93  5099.0 1168.62  5120.9 1168.49  5133.6 1171.06
  5162.3 1171.94  5236.5 1176.50  5250.6 1177.07  5266.4 1178.74  5288.0 1179.37
  5368.7 1184.32  5384.5 1186.02  5406.2 1187.23  5433.5 1190.48  5478.9 1192.96
#Mann=5,-1,0
  4718.7    0.12       0  4790.4    0.05       0  5047.5    0.03       0
  5087.8    0.05       0  5236.5    0.12       0
Bank Sta=5047.5,5087.8
Exp/Cntr=0.3,0.1

Type RM Length L Ch R = 1,10000,500,500,500
BEGIN DESCRIPTION:
BULLHEAD CREEK 20.0
END DESCRIPTION:
XS GIS Cut Line= 3
      2762405.65     10216103.09      2762905.81     10216476.04
      2763305.73     10216703.14
#Sta/Elev= 30
  4376.1 1191.89  4385.2 1191.35  4392.1 1190.72  4418.9 1189.90  4426.0 1188.82
  4504.4 1185.06  4573.6 1183.24  4599.4 1182.35  4662.9 1179.89  4731.8 1178.61
  4754.6 1178.35  4840.0 1172.72  4848.4 1172.87  4862.6 1171.51  4883.9 1168.01
  4912.5 1165.56  4924.6 1165.75  4969.3 1167.35  4983.9 1166.12  4984.7 1163.90
  4985.7 1163.40  5025.1 1163.90  5034.4 1164.99  5064.0 1165.91  5107.3 1164.49
  5137.9 1170.53  5182.3 1172.42  5312.0 1182.05  5373.3 1184.47  5459.9 1188.98
#Mann=10,-1,0
  4376.1    0.05       0  4385.2    0.12       0  4392.1    0.05       0
  4573.6    0.12       0  4599.4    0.05       0  4731.8    0.12       0
  4924.6    0.05       0  4984.7    0.05       0  5025.1    0.05       0
  5373.3    0.12       0
Bank Sta=4984.7,5025.1
Exp/Cntr=0.3,0.1

Type RM Length L Ch R = 1,9500,500,500,500
BEGIN DESCRIPTION:
BULLHEAD CREEK 19.0
END DESCRIPTION:
XS GIS Cut Line= 3
      2762205.72     10216853.12      2762708.73     10216912.50
      2763105.71     10216853.11
#Sta/Elev= 30
  4493.5 1184.35  4563.9 1183.68  4630.4 1182.00  4674.7 1180.99  4703.3 1178.72
  4735.1 1177.31  4745.2 1176.41  4776.0 1170.10  4796.3 1167.86  4815.7 1164.13
  4825.8 1163.14  4879.2 1164.33  4896.2 1163.85  4906.2 1160.95  4907.2 1160.45
  4946.6 1160.95  4956.7 1164.79  4986.9 1163.83  5000.0 1162.60  5007.0 1160.97
  5031.0 1161.05  5057.6 1162.72  5095.1 1168.67  5137.7 1170.69  5228.4 1174.90
  5233.5 1174.27  5280.0 1176.11  5290.1 1178.09  5302.8 1177.49  5401.4 1183.65
#Mann=7,-1,0
  4493.5    0.05       0  4630.4    0.12       0  4776.0    0.05       0
  4906.2    0.03       0  4946.6    0.05       0  5137.7    0.12       0
  5302.8    0.05       0
Bank Sta=4906.2,4946.6
Exp/Cntr=0.3,0.1

Type RM Length L Ch R = 1,9000,500,500,500
BEGIN DESCRIPTION:
BULLHEAD CREEK 18.0
END DESCRIPTION:
XS GIS Cut Line= 3
      2762155.64     10217603.14      2762508.60     10217360.88
      2763155.67     10217703.11
#Sta/Elev= 30
  4571.9 1184.63  4636.2 1181.15  4701.9 1173.78  4753.2 1170.84  4824.4 1166.57
  4830.4 1166.88  4845.3 1163.09  4876.7 1163.16  4902.2 1163.88  4932.0 1161.89
  4988.8 1162.29  5000.0 1161.69  5014.6 1159.53  5036.6 1160.67  5058.6 1160.30
  5060.3 1158.76  5061.3 1158.26  5100.8 1158.76  5119.0 1163.51  5124.6 1163.18
  5141.0 1165.89  5168.6 1160.38  5190.6 1167.41  5207.0 1168.60  5273.0 1168.82
  5333.4 1170.33  5471.8 1177.55  5531.4 1179.08  5696.2 1187.52  5732.0 1188.40
#Mann=5,-1,0
  4571.9    0.05       0  4753.2    0.12       0  4876.7    0.05       0
  5060.3    0.03       0  5100.8    0.05       0
Bank Sta=5060.3,5100.8
Exp/Cntr=0.3,0.1