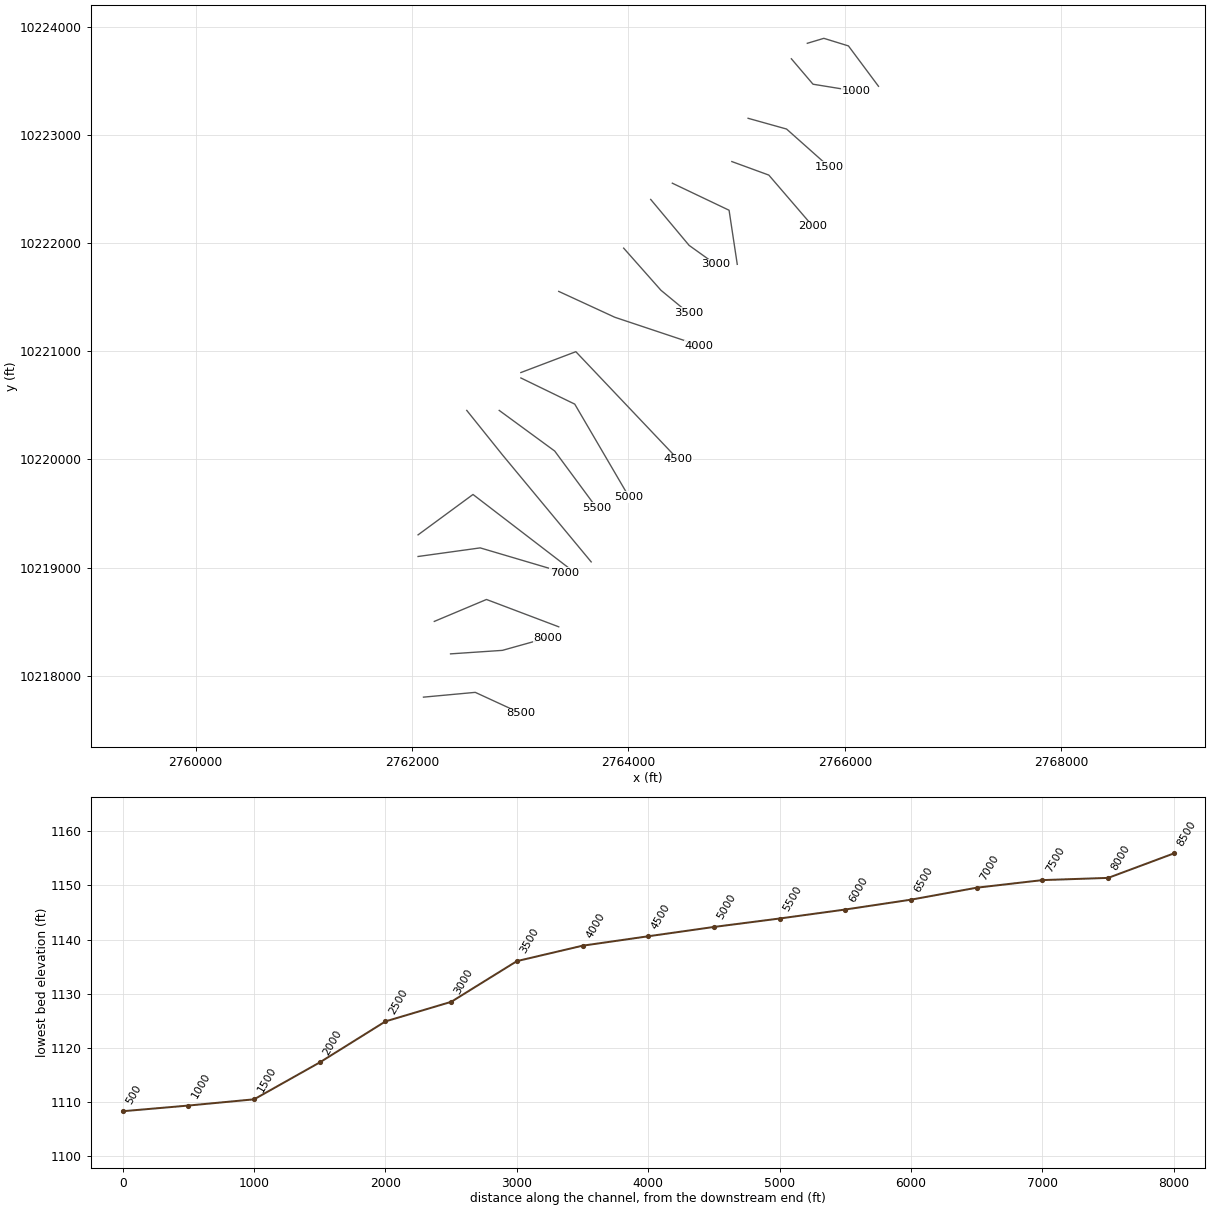
HEC-RAS study BULLHEAD CREEK.prj: BULLHEAD CREEK Base Level Engineering

--- BULLHEAD CREEK.g01 (geometry) --- (continued)

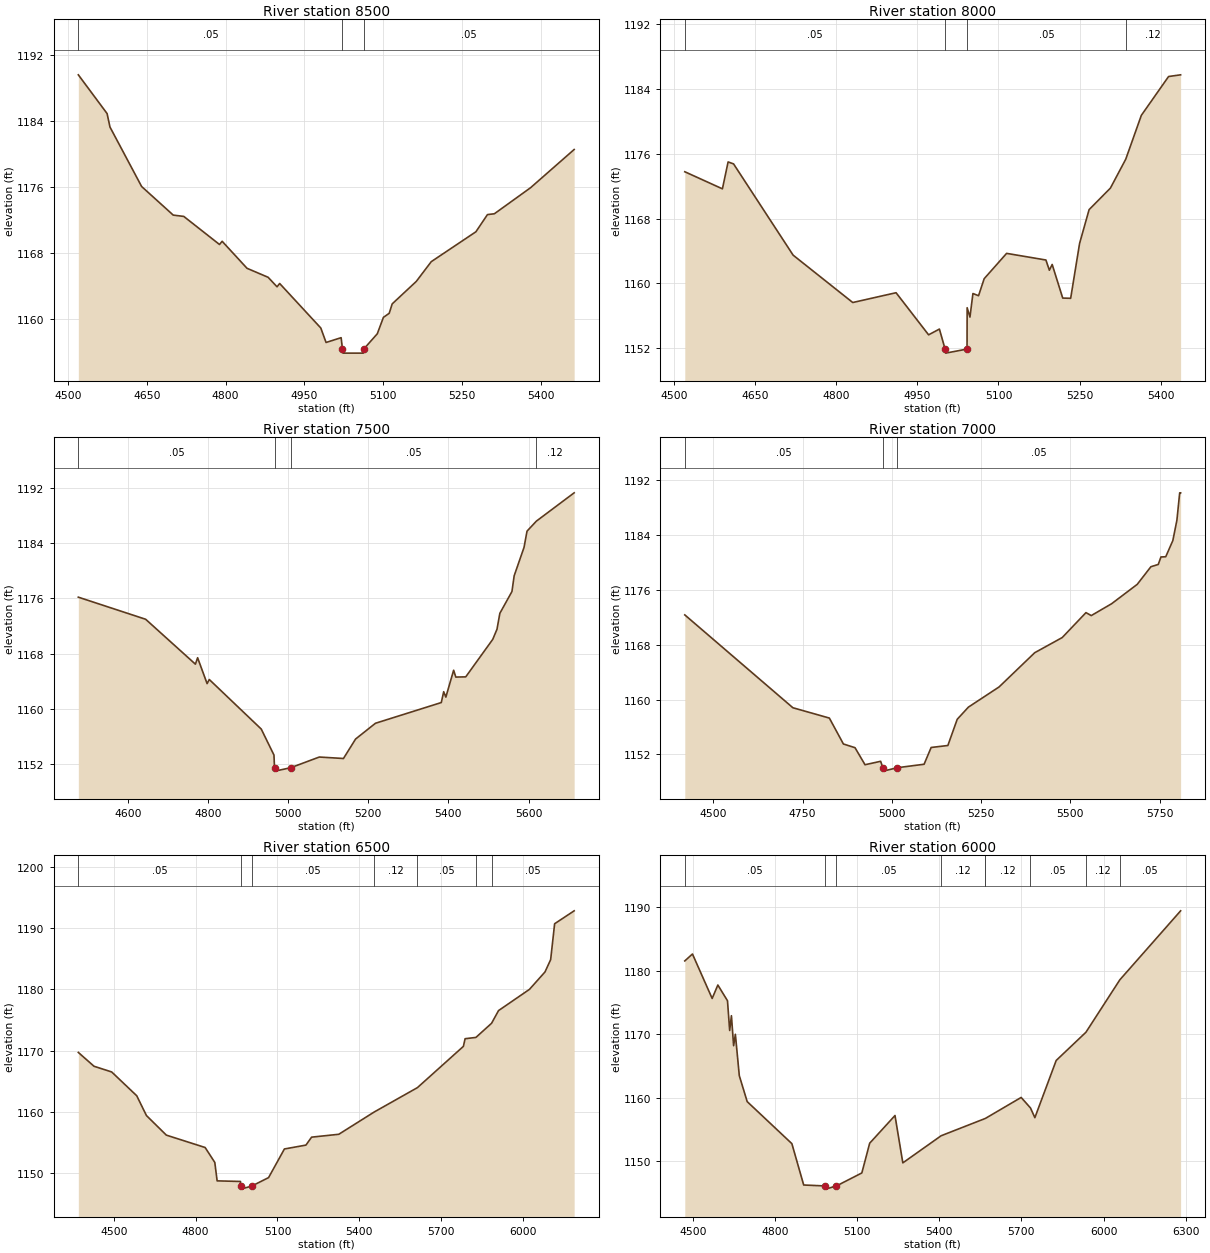
Type RM Length L Ch R = 1,8500,500,500,500
BEGIN DESCRIPTION:
BULLHEAD CREEK 17.0
END DESCRIPTION:
XS GIS Cut Line= 3
      2762105.64     10217803.11      2762584.20     10217847.32
      2763005.71     10217653.10
#Sta/Elev= 30
  4519.4 1189.60  4574.2 1184.91  4579.7 1183.28  4640.0 1176.08  4700.2 1172.62
  4720.3 1172.46  4788.4 1169.06  4793.4 1169.45  4840.8 1166.18  4881.0 1165.09
  4898.0 1163.94  4903.0 1164.34  4981.4 1158.95  4991.4 1157.20  5020.1 1157.78
  5022.7 1156.41  5023.7 1155.91  5062.3 1155.91  5063.3 1156.41  5089.0 1158.25
  5100.7 1160.24  5111.7 1160.73  5117.4 1161.87  5163.3 1164.59  5191.8 1166.98
  5276.9 1170.60  5298.9 1172.68  5312.1 1172.78  5381.0 1175.93  5464.1 1180.56
#Mann=3,-1,0
  4519.4    0.05       0  5022.7    0.03       0  5063.3    0.05       0
Bank Sta=5022.7,5063.3
Exp/Cntr=0.3,0.1

Type RM Length L Ch R = 1,8000,500,500,500
BEGIN DESCRIPTION:
BULLHEAD CREEK 16.0
END DESCRIPTION:
XS GIS Cut Line= 3
      2762355.73     10218203.11      2762834.84     10218235.48
      2763255.71     10218353.12
#Sta/Elev= 30
  4519.8 1173.79  4589.4 1171.68  4599.9 1175.00  4610.0 1174.76  4720.2 1163.49
  4830.5 1157.64  4910.6 1158.85  4970.8 1153.65  4990.8 1154.36  5001.3 1151.89
  5002.3 1151.39  5041.9 1151.89  5042.1 1157.00  5047.3 1155.84  5052.8 1158.75
  5063.2 1158.48  5073.6 1160.58  5115.1 1163.71  5187.8 1162.89  5194.2 1161.63
  5199.4 1162.34  5218.9 1158.19  5233.6 1158.16  5250.1 1164.94  5267.7 1169.11
  5307.1 1171.77  5335.5 1175.34  5364.3 1180.75  5414.7 1185.55  5437.0 1185.76
#Mann=4,-1,0
  4519.8    0.05       0  5001.3    0.03       0  5041.9    0.05       0
  5335.5    0.12       0
Bank Sta=5001.3,5041.9
Exp/Cntr=0.3,0.1

Type RM Length L Ch R = 1,7500,500,500,500
BEGIN DESCRIPTION:
BULLHEAD CREEK 15.0
END DESCRIPTION:
XS GIS Cut Line= 3
      2762205.67     10218503.11      2762688.00     10218705.82
      2763355.68     10218453.11
#Sta/Elev= 30
  4476.8 1176.17  4644.8 1172.97  4768.9 1166.47  4774.4 1167.40  4798.1 1163.65
  4803.5 1164.25  4933.2 1157.07  4964.9 1153.31  4966.3 1151.48  4967.3 1150.98
  5007.0 1151.48  5078.0 1153.02  5138.3 1152.81  5168.6 1155.63  5218.1 1157.91
  5382.4 1160.91  5388.4 1162.48  5393.8 1161.70  5413.2 1165.59  5418.6 1164.60
  5443.4 1164.63  5510.8 1170.06  5521.4 1171.53  5528.5 1173.83  5558.7 1176.99
  5564.2 1179.26  5588.9 1183.39  5596.3 1185.73  5619.6 1187.18  5713.9 1191.28
#Mann=4,-1,0
  4476.8    0.05       0  4966.3    0.05       0  5007.0    0.05       0
  5619.6    0.12       0
Bank Sta=4966.3,5007
Exp/Cntr=0.3,0.1

Type RM Length L Ch R = 1,7000,500,500,500
BEGIN DESCRIPTION:
BULLHEAD CREEK 14.0
END DESCRIPTION:
XS GIS Cut Line= 3
      2762055.70     10219103.11      2762629.92     10219182.63
      2763405.68     10218953.11
#Sta/Elev= 30
  4420.3 1172.31  4723.1 1158.80  4825.2 1157.30  4864.5 1153.53  4897.0 1152.99
  4925.1 1150.51  4968.8 1151.01  4975.0 1150.08  4976.0 1149.58  5015.7 1150.08
  5090.5 1150.58  5110.3 1153.02  5157.1 1153.31  5183.3 1157.12  5214.6 1158.89
  5300.6 1161.83  5400.4 1166.81  5477.3 1169.01  5543.9 1172.64  5558.7 1172.21
  5615.6 1173.93  5687.4 1176.75  5725.8 1179.32  5746.4 1179.65  5753.9 1180.74
  5767.3 1180.77  5787.2 1183.12  5798.6 1186.10  5806.4 1190.07  5809.0 1190.07
#Mann=3,-1,0
  4420.3    0.05       0  4975.0    0.03       0  5015.7    0.05       0
Bank Sta=4975,5015.7
Exp/Cntr=0.3,0.1

Type RM Length L Ch R = 1,6500,500,500,500
BEGIN DESCRIPTION:
BULLHEAD CREEK 13.0
END DESCRIPTION:
XS GIS Cut Line= 3
      2762055.64     10219303.08      2762563.25     10219676.23
      2763505.69     10218953.10
#Sta/Elev= 30
  4370.0 1169.70  4427.5 1167.44  4492.3 1166.51  4584.2 1162.62  4619.7 1159.39
  4692.7 1156.19  4834.9 1154.17  4870.4 1151.73  4878.9 1148.72  4964.5 1148.62
  4965.0 1147.87  4966.0 1147.37  5005.7 1147.87  5067.5 1149.25  5125.6 1153.93
  5204.4 1154.56  5225.3 1155.86  5325.0 1156.33  5454.5 1159.96  5613.3 1163.95
  5781.8 1170.69  5788.1 1171.94  5827.7 1172.15  5885.1 1174.46  5910.6 1176.53
  6024.0 1180.00  6080.9 1182.84  6101.7 1184.85  6116.3 1190.72  6187.9 1192.83
#Mann=7,-1,0
  4370.0    0.05       0  4965.0    0.03       0  5005.7    0.05       0
  5454.5    0.12       0  5613.3    0.05       0  5827.7    0.12       0
  5885.1    0.05       0
Bank Sta=4965,5005.7
Exp/Cntr=0.3,0.1

Type RM Length L Ch R = 1,6000,500,500,500
BEGIN DESCRIPTION:
BULLHEAD CREEK 12.0
END DESCRIPTION:
XS GIS Cut Line= 3
      2762505.68     10220453.12      2762837.37     10220039.75
      2763655.66     10219053.14
#Sta/Elev= 30
  4470.0 1181.54  4498.0 1182.63  4570.0 1175.62  4590.8 1177.74  4626.0 1175.26
  4634.0 1170.57  4640.4 1172.90  4648.4 1168.17  4654.8 1169.97  4669.2 1163.44
  4698.0 1159.35  4861.3 1152.72  4904.5 1146.20  4983.3 1146.05  4984.3 1145.55
  5024.0 1146.05  5116.9 1148.10  5145.6 1152.79  5238.1 1157.16  5266.7 1149.69
  5406.8 1153.97  5566.0 1156.66  5568.4 1156.70  5699.1 1160.01  5733.2 1158.35
  5749.2 1156.82  5827.1 1165.84  5935.8 1170.29  6059.7 1178.56  6281.8 1189.44
#Mann=9,-1,0
  4470.0    0.05       0  4983.3    0.03       0  5024.0    0.05       0
  5406.8    0.12       0  5566.0    0.05       0  5568.4    0.12       0
  5733.2    0.05       0  5935.8    0.12       0  6059.7    0.05       0
Bank Sta=4983.3,5024
Exp/Cntr=0.3,0.1

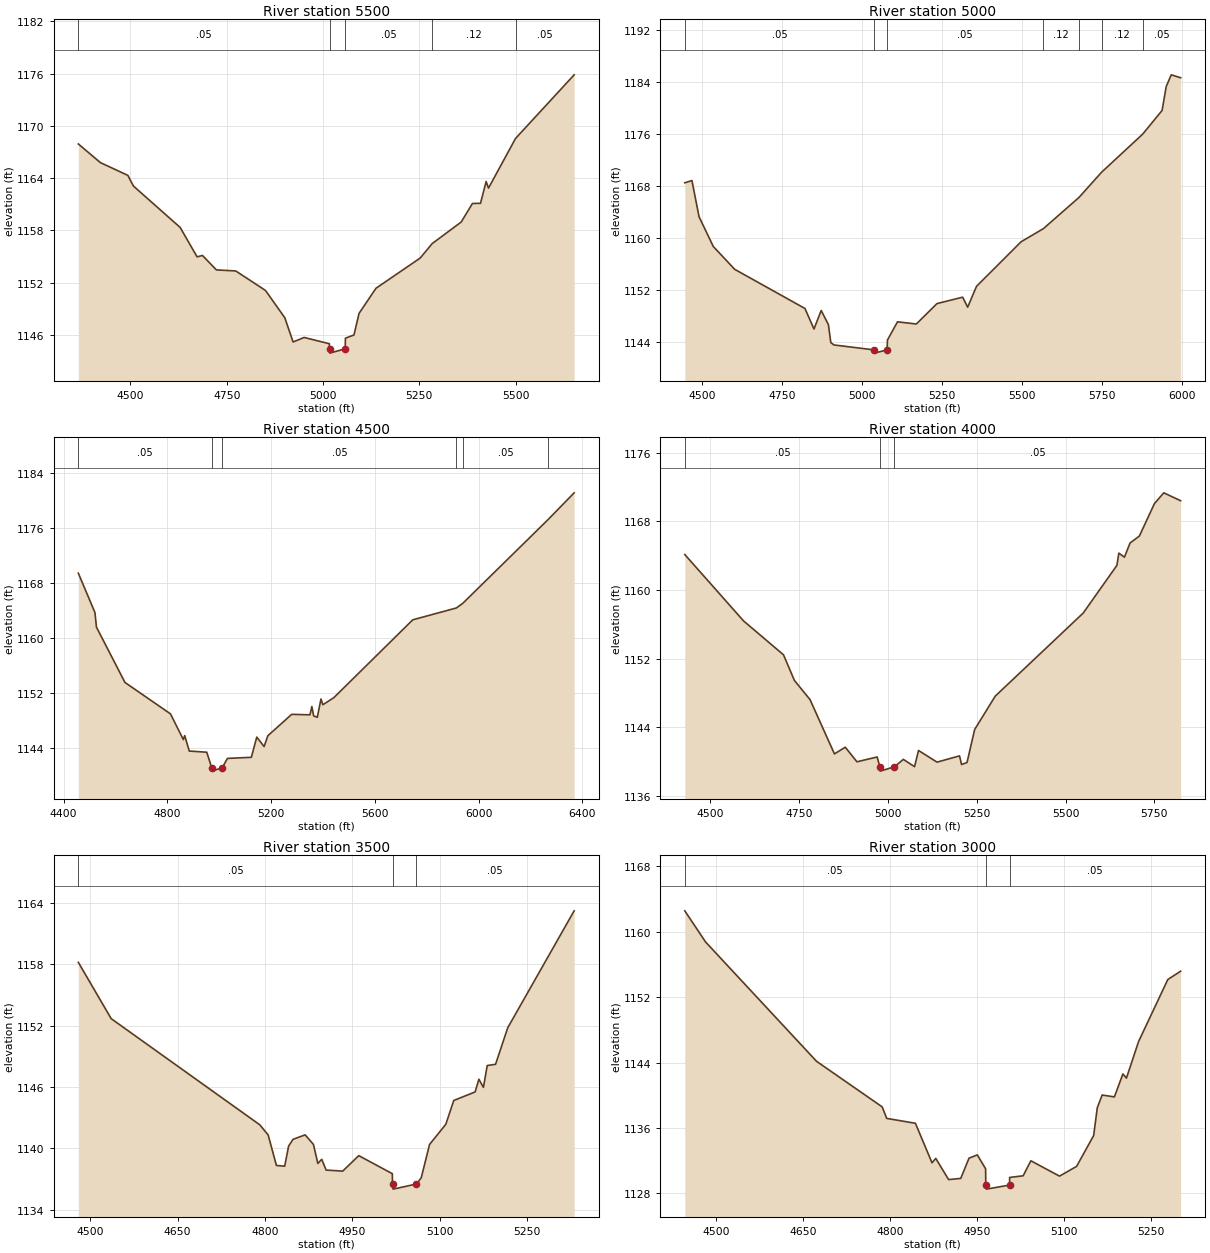
Type RM Length L Ch R = 1,5500,500,500,500
BEGIN DESCRIPTION:
BULLHEAD CREEK 11.0
END DESCRIPTION:
XS GIS Cut Line= 3
      2762805.67     10220453.12      2763318.27     10220077.82
      2763705.66     10219553.14
#Sta/Elev= 30
  4364.7 1167.92  4422.2 1165.77  4493.3 1164.31  4507.9 1163.08  4629.1 1158.33
  4673.1 1154.95  4687.0 1155.11  4723.3 1153.45  4773.5 1153.33  4850.7 1151.09
  4900.9 1147.95  4922.4 1145.17  4951.1 1145.69  5016.5 1144.97  5016.9 1144.39
  5017.9 1143.89  5057.7 1144.39  5058.2 1145.61  5080.4 1145.97  5093.7 1148.46
  5137.6 1151.34  5252.4 1154.81  5283.5 1156.47  5358.9 1158.95  5388.1 1161.08
  5409.0 1161.10  5423.6 1163.60  5429.8 1162.85  5500.0 1168.55  5652.2 1175.86
#Mann=5,-1,0
  4364.7    0.05       0  5016.9    0.03       0  5057.7    0.05       0
  5283.5    0.12       0  5500.0    0.05       0
Bank Sta=5016.9,5057.7
Exp/Cntr=0.3,0.1

Type RM Length L Ch R = 1,5000,500,500,500
BEGIN DESCRIPTION:
BULLHEAD CREEK 10.0
END DESCRIPTION:
XS GIS Cut Line= 3
      2763005.65     10220753.13      2763503.67     10220511.36
      2764005.69     10219653.10
#Sta/Elev= 30
  4446.4 1168.54  4468.7 1168.89  4490.9 1163.32  4535.4 1158.74  4602.1 1155.23
  4821.5 1149.20  4849.7 1146.04  4872.2 1148.89  4894.8 1146.71  4902.2 1143.96
  4911.8 1143.59  5037.1 1142.83  5038.1 1142.33  5078.0 1142.83  5079.1 1144.35
  5110.5 1147.15  5169.2 1146.81  5233.6 1149.95  5313.8 1150.94  5329.5 1149.40
  5357.1 1152.61  5496.1 1159.46  5566.2 1161.50  5677.2 1166.30  5747.3 1170.16
  5875.6 1176.02  5936.4 1179.67  5949.3 1183.35  5965.0 1185.16  5994.3 1184.71
#Mann=7,-1,0
  4446.4    0.05       0  5037.1    0.03       0  5078.0    0.05       0
  5566.2    0.12       0  5677.2    0.05       0  5747.3    0.12       0
  5875.6    0.05       0
Bank Sta=5037.1,5078
Exp/Cntr=0.3,0.1

Type RM Length L Ch R = 1,4500,500,500,500
BEGIN DESCRIPTION:
BULLHEAD CREEK 9.0
END DESCRIPTION:
XS GIS Cut Line= 3
      2763005.73     10220803.13      2763513.78     10220995.93
      2764455.66     10220003.13
#Sta/Elev= 30
  4456.6 1169.40  4520.7 1163.67  4526.5 1161.55  4636.4 1153.51  4811.9 1148.94
  4861.4 1145.20  4866.8 1145.78  4884.4 1143.53  4951.8 1143.36  4970.9 1141.11
  4971.9 1140.61  5011.8 1141.11  5031.5 1142.46  5123.7 1142.62  5144.7 1145.56
  5173.0 1144.18  5187.2 1145.75  5279.4 1148.87  5349.8 1148.80  5357.1 1150.00
  5364.0 1148.64  5378.1 1148.44  5392.3 1151.10  5399.5 1150.27  5442.0 1151.30
  5746.2 1162.62  5914.2 1164.34  5939.1 1165.02  6268.8 1177.23  6368.5 1181.09
#Mann=6,-1,0
  4456.6    0.05       0  4970.9    0.03       0  5011.8    0.05       0
  5914.2    0.12       0  5939.1    0.05       0  6268.8    0.12       0
Bank Sta=4970.9,5011.8
Exp/Cntr=0.3,0.1

Type RM Length L Ch R = 1,4000,500,500,500
BEGIN DESCRIPTION:
BULLHEAD CREEK 8.0
END DESCRIPTION:
XS GIS Cut Line= 3
      2763355.65     10221553.13      2763874.27     10221313.97
      2764655.68     10221053.11
#Sta/Elev= 30
  4428.9 1164.14  4594.1 1156.40  4706.6 1152.44  4737.3 1149.45  4781.3 1147.21
  4849.9 1140.88  4880.4 1141.66  4913.2 1139.96  4970.1 1140.52  4977.6 1139.37
  4978.6 1138.87  5018.5 1139.37  5043.7 1140.24  5075.3 1139.39  5086.4 1141.28
  5138.5 1139.92  5201.8 1140.65  5207.5 1139.64  5222.9 1139.88  5244.4 1143.73
  5302.3 1147.62  5549.7 1157.31  5644.6 1162.88  5650.0 1164.31  5665.7 1163.83
  5681.6 1165.49  5707.8 1166.30  5750.1 1170.08  5776.4 1171.34  5823.8 1170.42
#Mann=3,-1,0
  4428.9    0.05       0  4977.6    0.03       0  5018.5    0.05       0
Bank Sta=4977.6,5018.5
Exp/Cntr=0.3,0.1

Type RM Length L Ch R = 1,3500,500,500,500
BEGIN DESCRIPTION:
BULLHEAD CREEK 7.0
END DESCRIPTION:
XS GIS Cut Line= 3
      2763955.70     10221953.09      2764300.54     10221563.47
      2764555.70     10221353.10
#Sta/Elev= 30
  4479.7 1158.17  4536.1 1152.67  4791.2 1142.30  4805.5 1141.31  4819.7 1138.33
  4833.9 1138.26  4840.6 1140.22  4848.1 1140.88  4869.0 1141.32  4883.2 1140.39
  4890.8 1138.53  4897.5 1138.93  4905.0 1137.88  4933.5 1137.78  4961.0 1139.29
  5018.6 1137.53  5019.0 1136.52  5020.0 1136.02  5060.0 1136.52  5068.2 1137.12
  5082.5 1140.38  5110.4 1142.35  5124.1 1144.68  5160.7 1145.51  5167.2 1146.75
  5175.0 1145.96  5181.5 1148.09  5195.8 1148.21  5216.7 1151.78  5330.7 1163.20
#Mann=3,-1,0
  4479.7    0.05       0  5019.0    0.03       0  5060.0    0.05       0
Bank Sta=5019,5060
Exp/Cntr=0.3,0.1

Type RM Length L Ch R = 1,3000,500,500,500
BEGIN DESCRIPTION:
BULLHEAD CREEK 6.0
END DESCRIPTION:
XS GIS Cut Line= 3
      2764205.67     10222403.13      2764560.57     10221978.51
      2764805.68     10221803.12
#Sta/Elev= 30
  4446.6 1162.57  4482.4 1158.76  4673.7 1144.15  4786.9 1138.57  4794.7 1137.16
  4844.2 1136.56  4872.8 1131.72  4879.3 1132.26  4901.4 1129.67  4922.3 1129.81
  4936.6 1132.29  4950.9 1132.69  4965.2 1130.99  4965.5 1129.00  4966.5 1128.50
  5006.5 1129.00  5006.6 1129.93  5029.9 1130.13  5043.2 1131.97  5092.6 1130.09
  5122.0 1131.28  5151.5 1135.06  5157.7 1138.45  5166.1 1140.02  5187.2 1139.79
  5201.9 1142.60  5208.0 1142.09  5228.9 1146.56  5279.3 1154.16  5301.4 1155.18
#Mann=3,-1,0
  4446.6    0.05       0  4965.5    0.05       0  5006.5    0.05       0
Bank Sta=4965.5,5006.5
Exp/Cntr=0.3,0.1

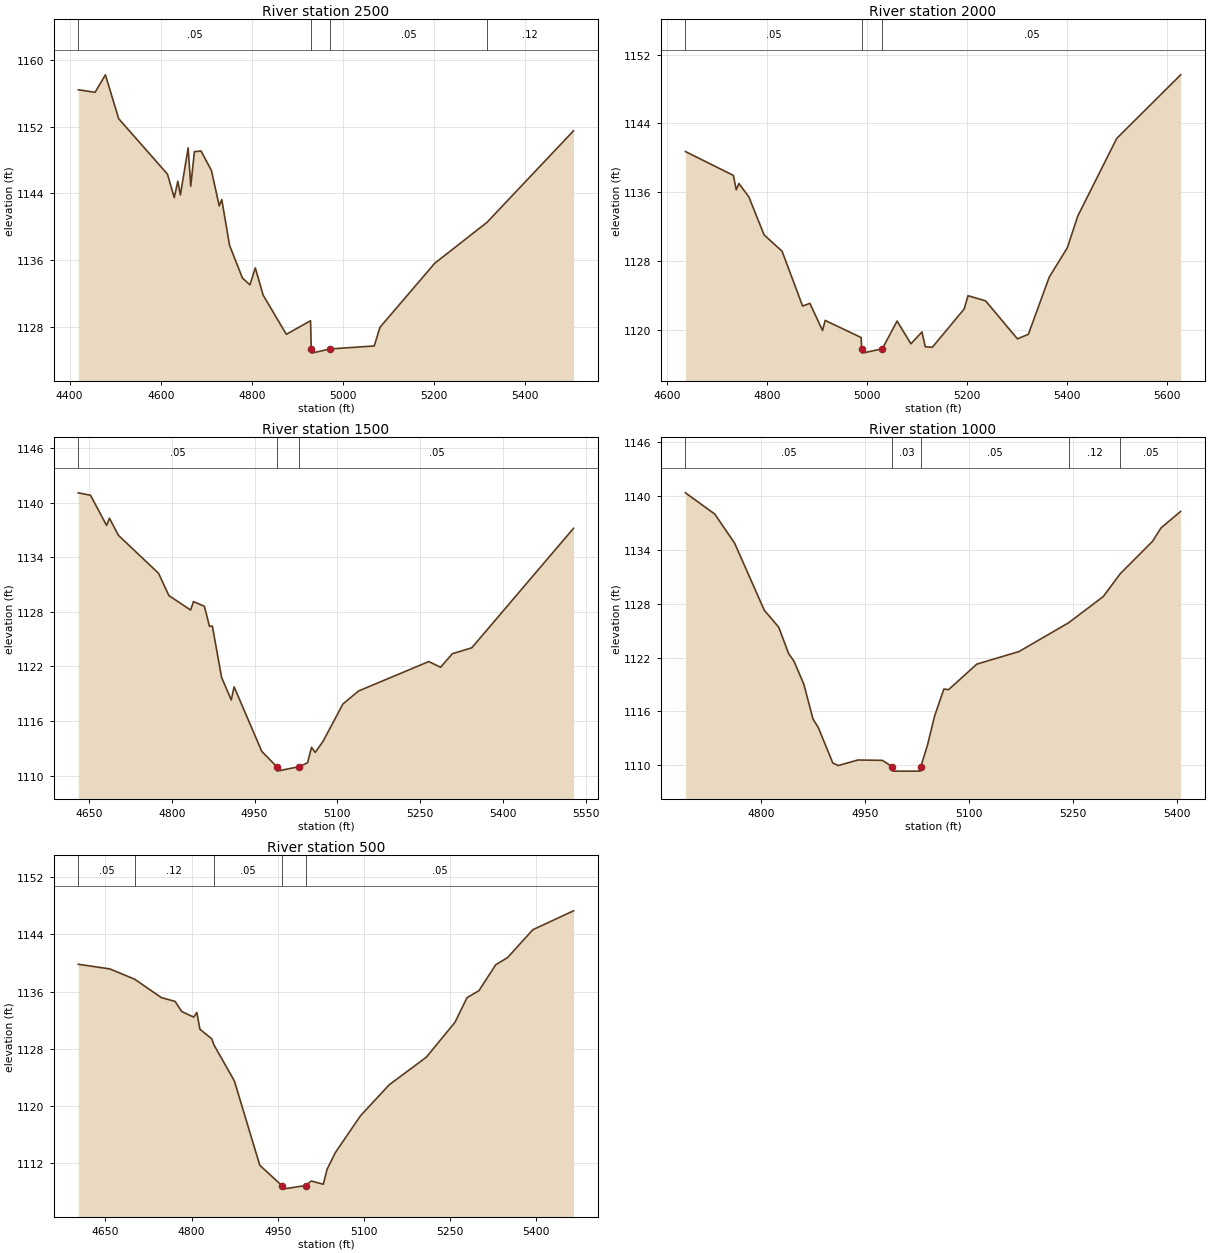
Type RM Length L Ch R = 1,2500,500,500,500
BEGIN DESCRIPTION:
BULLHEAD CREEK 5.0
END DESCRIPTION:
XS GIS Cut Line= 3
      2764405.69     10222553.11      2764930.00     10222303.26
      2765005.68     10221803.15
#Sta/Elev= 30
  4419.2 1156.41  4456.0 1156.11  4478.7 1158.20  4507.8 1152.95  4614.9 1146.31
  4629.7 1143.50  4637.6 1145.47  4643.2 1143.82  4660.3 1149.46  4665.9 1144.87
  4674.0 1149.01  4688.6 1149.08  4711.3 1146.75  4728.4 1142.51  4734.0 1143.27
  4751.1 1137.79  4779.4 1133.87  4795.8 1133.06  4807.6 1135.09  4824.8 1131.83
  4875.7 1127.14  4928.8 1128.77  4930.4 1125.39  4931.4 1124.89  4971.4 1125.39
  5068.6 1125.75  5081.1 1127.98  5201.2 1135.64  5315.9 1140.54  5505.8 1151.50
#Mann=4,-1,0
  4419.2    0.05       0  4930.4    0.03       0  4971.4    0.05       0
  5315.9    0.12       0
Bank Sta=4930.4,4971.4
Exp/Cntr=0.3,0.1

Type RM Length L Ch R = 1,2000,500,500,500
BEGIN DESCRIPTION:
BULLHEAD CREEK 4.0
END DESCRIPTION:
XS GIS Cut Line= 3
      2764955.64     10222753.13      2765297.22     10222628.20
      2765705.65     10222153.15
#Sta/Elev= 30
  4636.3 1140.73  4732.2 1137.96  4737.9 1136.29  4743.2 1137.02  4763.1 1135.47
  4793.6 1131.05  4829.5 1129.16  4870.6 1122.79  4885.2 1123.10  4910.4 1119.95
  4915.7 1121.12  4987.7 1119.13  4988.7 1117.82  4989.7 1117.32  5029.9 1117.82
  5059.5 1121.04  5087.2 1118.40  5109.2 1119.78  5115.8 1118.06  5130.0 1118.00
  5193.7 1122.45  5201.3 1123.99  5236.5 1123.39  5300.1 1118.98  5322.0 1119.50
  5363.7 1126.14  5399.9 1129.56  5420.8 1133.24  5498.7 1142.26  5626.5 1149.64
#Mann=3,-1,0
  4636.3    0.05       0  4988.7    0.03       0  5029.9    0.05       0
Bank Sta=4988.7,5029.9
Exp/Cntr=0.3,0.1

Type RM Length L Ch R = 1,1500,500,500,500
BEGIN DESCRIPTION:
BULLHEAD CREEK 3.0
END DESCRIPTION:
XS GIS Cut Line= 3
      2765105.71     10223153.10      2765461.30     10223053.80
      2765855.65     10222703.14
#Sta/Elev= 30
  4630.8 1141.08  4653.0 1140.81  4682.0 1137.50  4687.2 1138.29  4703.5 1136.41
  4776.1 1132.24  4794.9 1129.79  4834.2 1128.20  4839.4 1129.13  4859.2 1128.61
  4868.4 1126.41  4873.6 1126.44  4890.3 1120.80  4907.8 1118.32  4913.0 1119.76
  4963.0 1112.68  4990.0 1111.00  4991.0 1110.50  5031.2 1111.00  5046.0 1111.42
  5053.2 1113.12  5059.9 1112.56  5074.1 1113.78  5110.1 1117.88  5138.5 1119.31
  5265.6 1122.54  5286.9 1121.91  5308.2 1123.40  5343.4 1124.05  5527.7 1137.18
#Mann=3,-1,0
  4630.8    0.05       0  4990.0    0.03       0  5031.2    0.05       0
Bank Sta=4990,5031.2
Exp/Cntr=0.3,0.1

Type RM Length L Ch R = 1,1000,500,500,500
BEGIN DESCRIPTION:
BULLHEAD CREEK 2.0
END DESCRIPTION:
XS GIS Cut Line= 3
      2765505.71     10223703.08      2765705.85     10223468.04
      2766105.71     10223403.11
#Sta/Elev= 30
  4691.3 1140.35  4733.5 1137.99  4762.1 1134.76  4804.9 1127.28  4825.8 1125.38
  4840.0 1122.45  4847.8 1121.59  4862.0 1119.02  4875.2 1115.15  4882.9 1114.19
  4903.7 1110.26  4911.4 1109.97  4940.0 1110.59  4975.1 1110.55  4989.3 1109.85
  4990.3 1109.35  5029.6 1109.35  5030.6 1109.85  5040.4 1112.31  5050.5 1115.50
  5063.8 1118.49  5070.7 1118.43  5111.3 1121.27  5172.1 1122.67  5243.7 1125.88
  5293.6 1128.80  5317.9 1131.33  5364.5 1134.94  5376.8 1136.44  5405.1 1138.28
#Mann=5,-1,0
  4691.3    0.05       0  4989.3    0.03       0  5030.6    0.05       0
  5243.7    0.12       0  5317.9    0.05       0
Bank Sta=4989.3,5030.6
Exp/Cntr=0.3,0.1

Type RM Length L Ch R = 1,500,0,0,0
BEGIN DESCRIPTION:
BULLHEAD CREEK 1.0
END DESCRIPTION:
XS GIS Cut Line= 4
      2765653.24     10223846.26      2765805.95     10223892.07
      2766033.17     10223822.05      2766311.13     10223448.78
#Sta/Elev= 30
  4602.8 1139.82  4657.6 1139.17  4701.1 1137.72  4747.4 1135.15  4771.4 1134.61
  4782.9 1133.20  4803.8 1132.41  4809.3 1133.06  4814.6 1130.72  4835.2 1129.37
  4839.1 1128.51  4874.7 1123.46  4918.9 1111.65  4957.3 1108.80  4958.3 1108.30
  4998.6 1108.80  5008.7 1109.44  5029.6 1108.98  5036.1 1111.07  5050.4 1113.40
  5094.2 1118.57  5144.3 1122.92  5209.0 1126.79  5259.0 1131.69  5279.8 1135.13
  5300.7 1136.12  5329.9 1139.75  5350.7 1140.77  5394.5 1144.66  5465.4 1147.31
#Mann=5,-1,0
  4602.8    0.05       0  4701.1    0.12       0  4839.1    0.05       0
  4957.3    0.03       0  4998.6    0.05       0
Bank Sta=4957.3,4998.6
Exp/Cntr=0.3,0.1

Chan Stop Cuts=-1