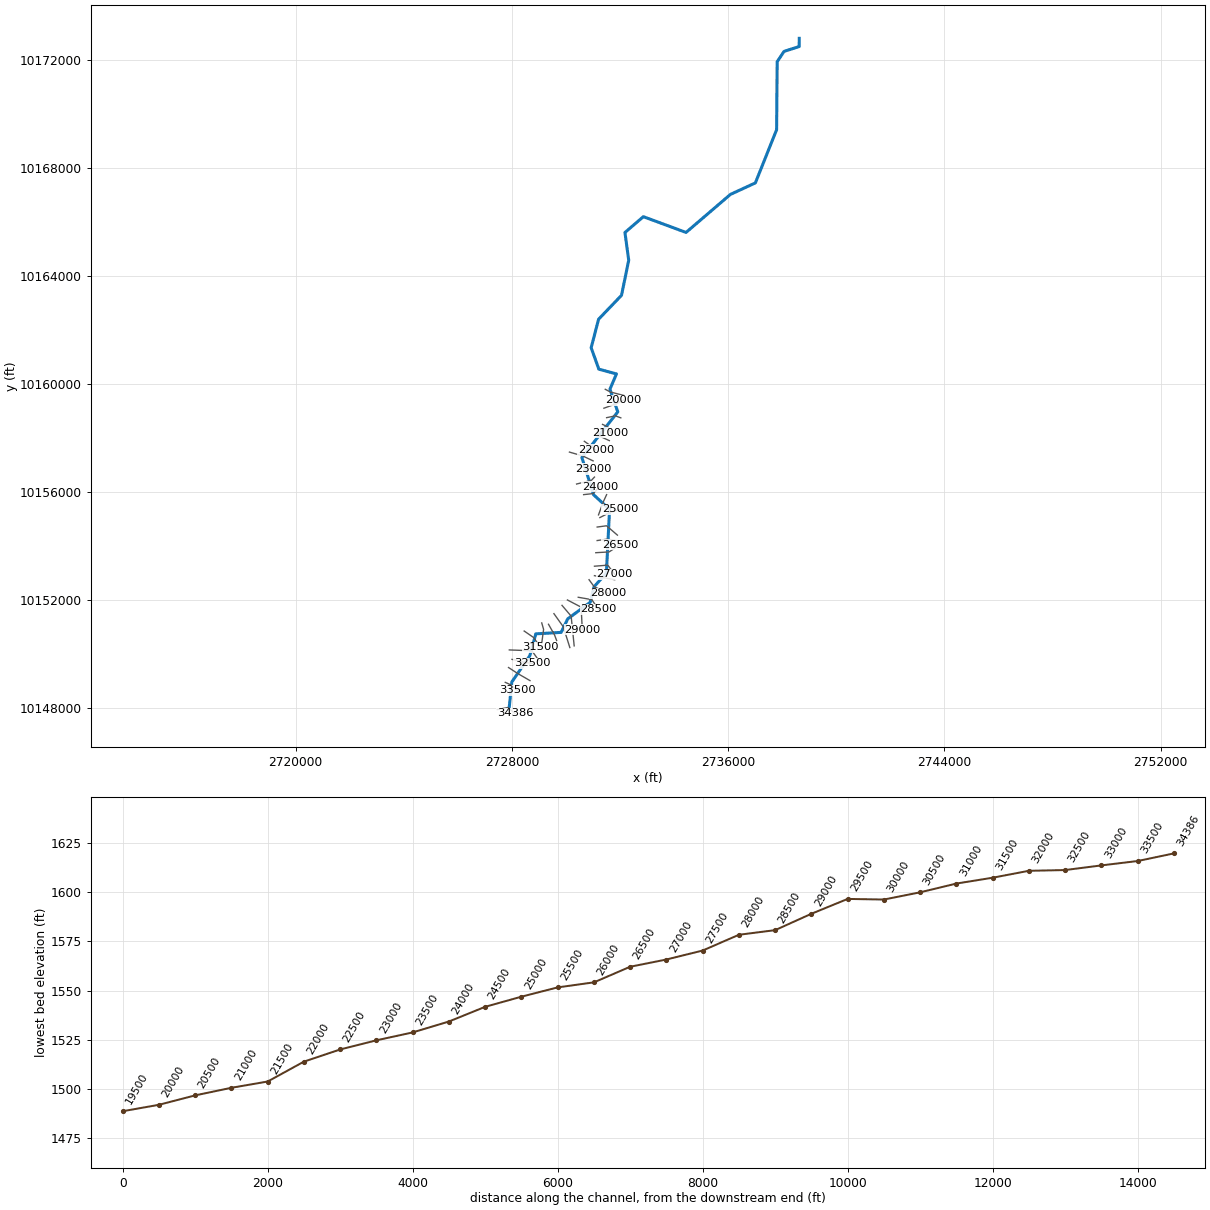
--- CHERRY SPRING CREEK.prj (project) ---

Proj Title=CHERRY SPRING CREEK Base Level Engineering
Current Plan=p01
Default Exp/Contr=0.3,0.1
English Units
Geom File=g01
Flow File=f01
Plan File=p01
Y Axis Title=Elevation
X Axis Title(PF)=Main Channel Distance
X Axis Title(XS)=Station
BEGIN DESCRIPTION:
CHERRY SPRING CREEK
END DESCRIPTION:
DSS Export Rating Curves= 0
DSS Export Rating Curve Sorted= 0
DSS Export Volume Flow Curves= 0
DXF OffsetX= 0
DXF OffsetY= 0
DXF ScaleX= 1
DXF ScaleY= 10

--- CHERRY SPRING CREEK.p01 (plan) ---

Plan Title=Multiple Run
Short Identifier=Multiple
Geom File=g01
Flow File=f01
Subcritical Flow
K Sum by GR= 0
Std Step Tol= 0.01
Critical Tol= 0.01
Num of Std Step Trials= 20
Max Error Tol= 0.3
Flow Tol Ratio= 0.001
Split Flow NTrial= 30
Split Flow Tol= 0.02
Split Flow Ratio= 0.02
Log Output Level= 0
Friction Slope Method= 1
Unsteady Friction Slope Method= 2
Unsteady Bridges Friction Slope Method= 1
Parabolic Critical Depth
Global Vel Dist=  1 , 1 , 1
Global Log Level= 0
CheckData=True
Encroach Param= -1, 0, 0, 0
BEGIN DESCRIPTION:
Multiple Run
END DESCRIPTION:

--- CHERRY SPRING CREEK.f01 (steady flow) ---

Flow Title=Multiple
Program Version=4.10
Number of Profiles= 7
Profile Names=10-year,25-year,50-year,1pct_min,100-year,1pct_plu,500-year
River Rch & RM=CHERRY SPRING CR,Reach-1         ,34386
    3030    5614   10251    7009   14972   31979   20813
River Rch & RM=CHERRY SPRING CR,Reach-1         ,28500
    3456    6459   11718    8036   17115   36452   23644
River Rch & RM=CHERRY SPRING CR,Reach-1         ,28000
    4375    8270   14821   10073   21664   46590   29717
River Rch & RM=CHERRY SPRING CR,Reach-1         ,24000
    4781    9068   16225   10961   23733   51386   32512
River Rch & RM=CHERRY SPRING CR,Reach-1         ,21000
    5199    9905   17649   11671   25879   57385   35486
River Rch & RM=CHERRY SPRING CR,Reach-1         ,12500
    5566   10627   18880   12402   27693   61837   37927
River Rch & RM=CHERRY SPRING CR,Reach-1         ,9000
    5903   11281   19929   13038   29212   65451   39920
River Rch & RM=CHERRY SPRING CR,Reach-1         ,7500
    6096   11677   20460   13189   30011   68292   40999
Boundary for River Rch & Prof#=CHERRY SPRING CR,Reach-1         , 1
Up Type= 0
Dn Type= 3
Dn Slope=0.0005
Boundary for River Rch & Prof#=CHERRY SPRING CR,Reach-1         , 2
Up Type= 0
Dn Type= 3
Dn Slope=0.0005
Boundary for River Rch & Prof#=CHERRY SPRING CR,Reach-1         , 3
Up Type= 0
Dn Type= 3
Dn Slope=0.0005
Boundary for River Rch & Prof#=CHERRY SPRING CR,Reach-1         , 4
Up Type= 0
Dn Type= 3
Dn Slope=0.0005
Boundary for River Rch & Prof#=CHERRY SPRING CR,Reach-1         , 5
Up Type= 0
Dn Type= 3
Dn Slope=0.0005
Boundary for River Rch & Prof#=CHERRY SPRING CR,Reach-1         , 6
Up Type= 0
Dn Type= 3
Dn Slope=0.0005
Boundary for River Rch & Prof#=CHERRY SPRING CR,Reach-1         , 7
Up Type= 0
Dn Type= 3
Dn Slope=0.0005
DSS Import GetInterval= 0
DSS Import GetPeak= 0
DSS Import FillOption= 0

--- CHERRY SPRING CREEK.g01 (geometry) ---

Geom Title=Existing Conditions
Program Version=4.10

River Reach=CHERRY SPRING CR,Reach-1
Reach XY= 30
      2727896.75       10147970.      2727998.75       10148966.
       2728665.5       10149941.      2728886.25       10150749.
        2729824.       10150803.       2730065.5       10151302.
        2730900.       10151918.       2731038.5       10152490.
      2731497.75       10152999.        2731615.       10155356.
        2731025.       10155897.       2730590.5       10157278.
      2731919.75       10158968.      2731628.25       10159807.
        2731871.       10160372.        2731218.       10160549.
      2730934.25       10161342.        2731208.       10162397.
      2732056.75       10163283.       2732323.5       10164582.
        2732184.       10165608.      2732865.25       10166195.
      2734444.25       10165611.        2736088.       10167020.
       2737009.5       10167445.        2737795.       10169414.
      2737815.75       10171931.        2738070.       10172314.
      2738632.25       10172495.       2738633.5       10172798.

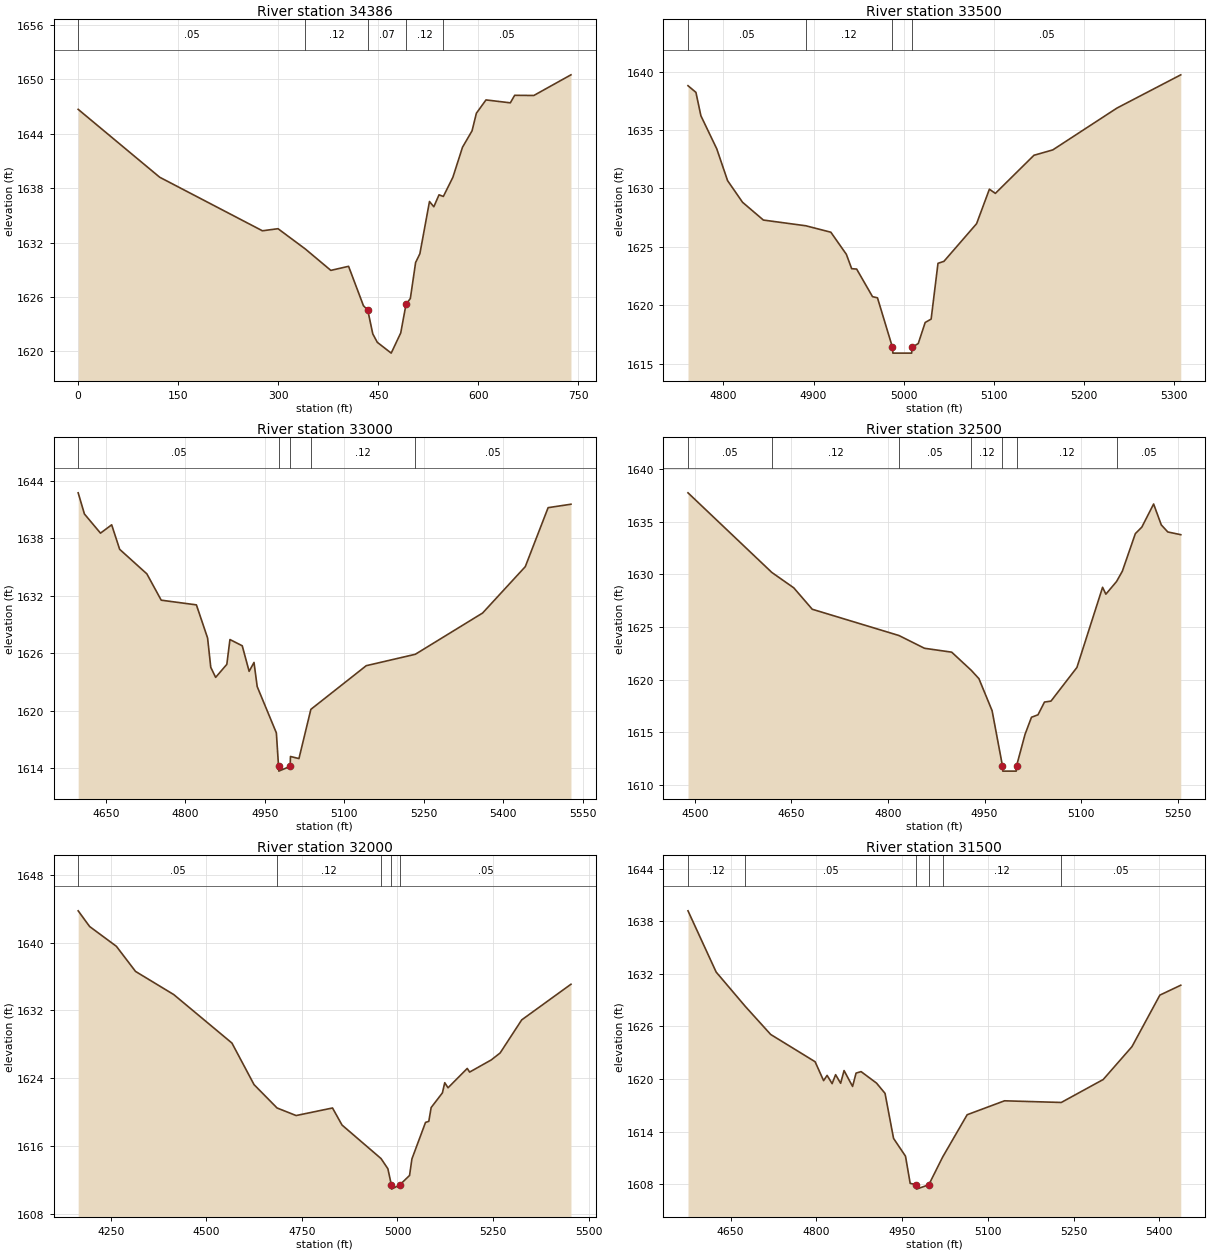
Type RM Length L Ch R = 1 ,34386   ,500,500,500
BEGIN DESCRIPTION:
CHERRY SPRING CREEK 68.0
END DESCRIPTION:
XS GIS Cut Line= 3
      2727461.71     10147944.26      2727851.03     10148021.09
      2728115.35     10147804.07
#Sta/Elev= 30
       0  1646.7   122.2 1639.21   276.2  1633.3   299.6 1633.53   340.4  1631.3
   378.8 1628.93   405.4 1629.38   427.7 1625.03   434.1 1624.56   441.7 1621.92
   448.5 1620.99   469.3  1619.8   483.6 1622.03   491.5 1625.18     498 1625.83
   505.9  1629.8   512.3 1630.77   526.7 1636.53   533.2 1635.95     541 1637.27
   547.5 1637.09   561.8 1639.21   576.2 1642.52   590.5 1644.33     597 1646.27
   611.4 1647.74   647.9 1647.42   654.4 1648.25   683.1 1648.23   738.8 1650.51
#Mann= 5 ,-1 , 0
       0     .05       0   340.4     .12       0   434.1     .07       0
   491.5     .12       0   547.5     .05       0
Bank Sta=434.1,491.5
XS Rating Curve= 0 ,0
Exp/Cntr=0.3,0.1

Type RM Length L Ch R = 1 ,33500   ,500,500,500
BEGIN DESCRIPTION:
CHERRY SPRING CREEK 67.0
END DESCRIPTION:
XS GIS Cut Line= 3
       2727755.7     10148953.11       2727973.6     10148854.44
      2728205.65     10148653.14
#Sta/Elev= 30
  4760.8 1638.79  4769.6 1638.22  4775.1 1636.22  4792.7 1633.39  4804.7 1630.67
  4821.3 1628.82  4844.4  1627.3  4891.5 1626.81  4919.2 1626.26  4936.4 1624.37
  4942.3 1623.14  4947.8 1623.11  4965.4 1620.75  4970.9 1620.65  4987.5 1616.42
    4988 1615.92  5008.8 1615.92  5009.3 1616.42  5016.1 1616.74  5023.8 1618.54
  5030.4 1618.83    5038  1623.6  5044.6 1623.77  5080.8 1626.99    5095 1629.94
  5101.6 1629.58  5144.4 1632.84  5165.3  1633.3  5236.5 1636.88  5307.2 1639.72
#Mann= 4 ,-1 , 0
  4760.8     .05       0  4891.5     .12       0  4987.5     .07       0
  5009.3     .05       0
Bank Sta=4987.5,5009.3
XS Rating Curve= 0 ,0
Exp/Cntr=0.3,0.1

Type RM Length L Ch R = 1 ,33000   ,500,500,500
BEGIN DESCRIPTION:
CHERRY SPRING CREEK 66.0
END DESCRIPTION:
XS GIS Cut Line= 3
      2727876.39     10149501.74      2728213.08     10149282.09
        2728670.      10149017.7
#Sta/Elev= 30
    4598 1642.76  4609.8 1640.55  4640.1 1638.55  4661.2 1639.42  4676.3 1636.86
  4727.6  1634.3  4754.7 1631.55  4821.1 1631.06  4842.2  1627.6  4848.2 1624.54
  4857.4 1623.49  4878.5 1624.85  4884.4 1627.44  4907.6 1626.79  4920.6 1624.12
  4929.8 1625.05  4935.8 1622.53    4972 1617.69  4976.1  1614.2  4976.6  1613.7
    4998  1614.2  4998.6 1615.23  5014.6 1615.01  5037.1 1620.15  5141.6 1624.71
  5234.2  1625.9  5361.2 1630.21  5441.7 1635.05  5484.8 1641.21  5527.9 1641.57
#Mann= 5 ,-1 , 0
    4598     .05       0  4976.1     .05       0    4998     .05       0
  5037.1     .12       0  5234.2     .05       0
Bank Sta=4976.1,4998
XS Rating Curve= 0 ,0
Exp/Cntr=0.3,0.1

Type RM Length L Ch R = 1 ,32500   ,500,500,500
BEGIN DESCRIPTION:
CHERRY SPRING CREEK 65.0
END DESCRIPTION:
XS GIS Cut Line= 3
      2728005.67     10149803.12      2728502.83     10149685.85
      2728755.72     10149653.11
#Sta/Elev= 30
  4489.2 1637.72  4619.5 1630.17  4653.6 1628.71  4682.3 1626.68    4817 1624.19
  4856.7 1622.98    4899 1622.61  4929.4 1620.89  4941.3  1620.1  4961.8 1617.06
  4977.9 1611.83  4978.4 1611.33  4999.3 1611.33  4999.8 1611.83    5013 1614.82
    5023 1616.44  5033.1 1616.67  5043.2 1617.88  5053.3 1617.97  5093.6 1621.16
  5133.5 1628.76  5138.6 1628.11  5155.2 1629.31  5164.2 1630.29  5184.4 1633.85
  5194.5 1634.47  5212.8 1636.66  5224.7 1634.68  5234.8 1634.01    5255 1633.75
#Mann= 7 ,-1 , 0
  4489.2     .05       0  4619.5     .12       0    4817     .05       0
  4929.4     .12       0  4977.9     .07       0  4999.8     .12       0
  5155.2     .05       0
Bank Sta=4977.9,4999.8
XS Rating Curve= 0 ,0
Exp/Cntr=0.3,0.1

Type RM Length L Ch R = 1 ,32000   ,500,500,500
BEGIN DESCRIPTION:
CHERRY SPRING CREEK 64.0
END DESCRIPTION:
XS GIS Cut Line= 3
      2727905.71     10150153.11      2728740.72     10150121.73
       2729005.7     10149753.09
#Sta/Elev= 30
  4164.4 1643.74  4194.4 1641.89  4264.4 1639.56  4314.5  1636.6  4414.6 1633.87
  4566.8 1628.16  4624.7 1623.26  4684.9 1620.51  4734.8 1619.62    4830 1620.51
  4854.9  1618.5    4957 1614.55  4974.9 1613.35    4984 1611.45  4984.5 1610.95
    5006 1611.45  5031.6 1612.56  5037.8 1614.51  5073.4 1618.81    5082 1618.94
  5088.1 1620.56  5117.6 1622.29  5123.7 1623.49  5132.3 1622.89  5182.6 1625.17
  5188.8 1624.74  5245.3 1626.17  5268.6 1626.99  5325.1 1630.89    5454 1635.09
#Mann= 5 ,-1 , 0
  4164.4     .05       0  4684.9     .12       0    4957     .05       0
    4984     .05       0    5006     .05       0
Bank Sta=4984,5006
XS Rating Curve= 0 ,0
Exp/Cntr=0.3,0.1

Type RM Length L Ch R = 1 ,31500   ,500,500,500
BEGIN DESCRIPTION:
CHERRY SPRING CREEK 63.0
END DESCRIPTION:
XS GIS Cut Line= 3
      2728455.68     10150853.11      2728805.24      10150611.9
      2729055.71     10150253.07
#Sta/Elev= 30
  4575.3 1639.19  4624.6  1632.2  4675.9 1628.26    4720 1625.08  4797.7 1621.97
  4812.6 1619.81  4818.7 1620.41  4827.5 1619.47  4833.6 1620.49  4842.4 1619.51
  4848.4 1620.96  4863.3 1619.15  4869.4 1620.67  4878.2 1620.84  4905.2 1619.53
  4920.1 1618.36    4935 1613.22  4955.9 1611.19  4964.1 1608.09  4974.6 1607.93
  4975.1 1607.43  4996.7 1607.93  5020.9 1611.09  5063.8 1615.92  5129.2 1617.51
  5228.5 1617.32  5301.9 1619.94  5352.2 1623.69    5401 1629.57  5437.6  1630.7
#Mann= 6 ,-1 , 0
  4575.3     .12       0  4675.9     .05       0  4974.6     .05       0
  4996.7     .05       0  5020.9     .12       0  5228.5     .05       0
Bank Sta=4974.6,4996.7
XS Rating Curve= 0 ,0
Exp/Cntr=0.3,0.1

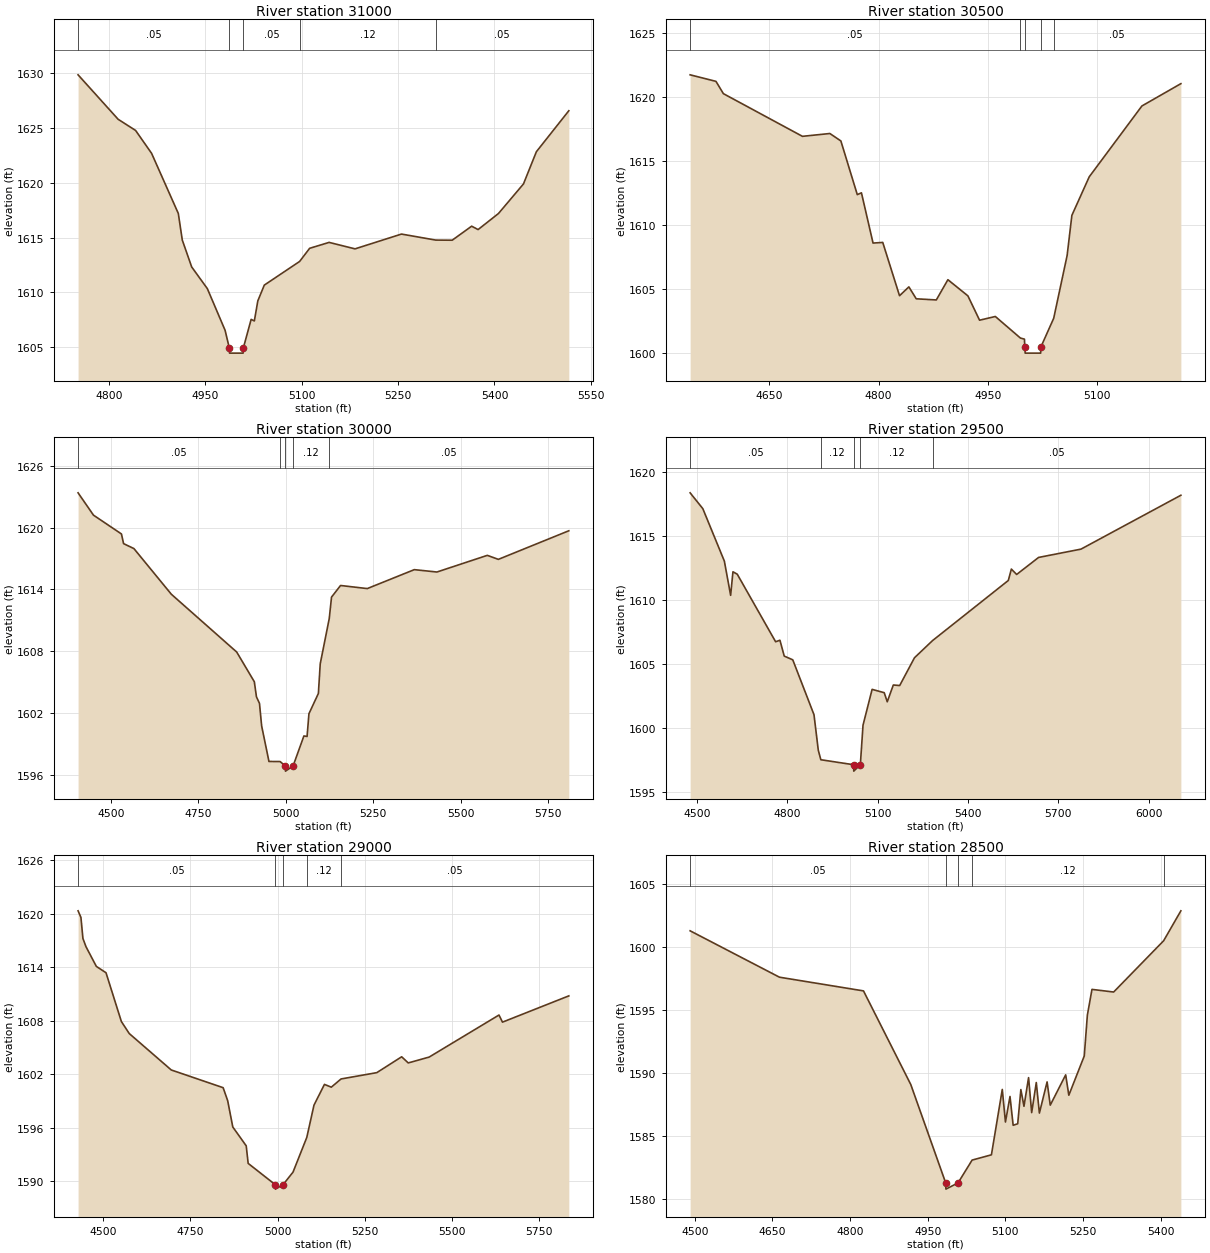
Type RM Length L Ch R = 1 ,31000   ,500,500,500
BEGIN DESCRIPTION:
CHERRY SPRING CREEK 62.0
END DESCRIPTION:
XS GIS Cut Line= 3
      2729105.68     10151153.14       2729174.1     10150914.35
      2729105.68     10150403.11
#Sta/Elev= 30
  4751.6 1629.87    4814 1625.81  4841.2 1624.79  4866.1  1622.7  4907.7 1617.21
  4913.9 1614.78  4928.5 1612.33  4952.9 1610.35  4980.5 1606.55    4987 1604.96
  4987.5 1604.46  5008.6 1604.46  5009.1 1604.96  5021.1 1607.54  5026.1  1607.4
  5031.5 1609.23  5041.6 1610.67  5096.6 1612.83  5112.2 1614.03  5142.5 1614.57
  5182.9 1613.98  5255.2 1615.33  5308.6 1614.78  5334.2 1614.77  5364.5 1616.05
  5374.5 1615.74  5406.3 1617.21  5445.2 1619.91  5465.3 1622.85  5515.8 1626.59
#Mann= 5 ,-1 , 0
  4751.6     .05       0    4987     .05       0  5009.1     .05       0
  5096.6     .12       0  5308.6     .05       0
Bank Sta=4987,5009.1
XS Rating Curve= 0 ,0
Exp/Cntr=0.3,0.1

Type RM Length L Ch R = 1 ,30500   ,500,500,500
BEGIN DESCRIPTION:
CHERRY SPRING CREEK 61.0
END DESCRIPTION:
XS GIS Cut Line= 3
      2729355.67     10151103.14      2729580.59     10150703.95
      2729655.68     10150503.13
#Sta/Elev= 30
  4541.8 1621.72  4577.2 1621.21  4587.4 1620.25  4695.7 1616.92  4733.3 1617.14
  4748.4 1616.56  4770.9 1612.37  4776.6 1612.51  4792.5 1608.59  4805.8 1608.64
  4828.8 1604.48  4841.6 1605.17  4851.7 1604.24  4879.2 1604.15  4895.1 1605.73
  4922.5 1604.47  4938.5 1602.57  4960.1 1602.86  4994.4 1601.18    5000 1601.09
  5000.5  1600.5    5001    1600  5022.2    1600  5022.7  1600.5  5040.1 1602.72
  5058.5 1607.62    5065 1610.75  5088.8 1613.76    5161 1619.29  5214.4 1621.03
#Mann= 5 ,-1 , 0
  4541.8     .05       0  4994.4     .12       0  5000.5     .07       0
  5022.7     .12       0  5040.1     .05       0
Bank Sta=5000.5,5022.7
XS Rating Curve= 0 ,0
Exp/Cntr=0.3,0.1

Type RM Length L Ch R = 1 ,30000   ,500,500,500
BEGIN DESCRIPTION:
CHERRY SPRING CREEK 60.0
END DESCRIPTION:
XS GIS Cut Line= 3
      2729556.68     10151496.15      2729901.09     10151012.56
      2730145.22     10150240.96
#Sta/Elev= 30
  4406.3 1623.39  4450.3 1621.22  4530.3 1619.39  4536.4 1618.45  4565.9 1617.97
  4672.9 1613.53  4859.8 1607.91  4910.2 1605.02  4916.3 1603.55  4924.9 1602.92
  4931.1 1600.73    4952 1597.27  4983.9 1597.26  4998.8 1596.83  4999.3 1596.33
    5021 1596.83  5051.9 1599.75    5061  1599.7  5066.3 1601.91  5093.3 1603.88
  5098.6 1606.76  5124.4 1611.17  5130.9 1613.25  5156.7 1614.38  5233.1 1614.08
  5367.5 1615.92  5432.2 1615.69  5576.3 1617.31  5607.8 1616.92  5809.3  1619.7
#Mann= 5 ,-1 , 0
  4406.3     .05       0  4983.9     .12       0  4998.8     .07       0
    5021     .12       0  5124.4     .05       0
Bank Sta=4998.8,5021
XS Rating Curve= 0 ,0
Exp/Cntr=0.3,0.1

Type RM Length L Ch R = 1 ,29500   ,500,500,500
BEGIN DESCRIPTION:
CHERRY SPRING CREEK 59.0
END DESCRIPTION:
XS GIS Cut Line= 3
      2729855.71     10151803.08       2730193.5     10151404.59
      2730305.69     10150303.09
#Sta/Elev= 30
  4477.6 1618.39  4519.8 1617.15  4591.3 1613.05  4612.1 1610.38  4619.8 1612.22
  4634.1 1612.03  4761.5 1606.75  4775.8 1606.87  4790.1 1605.63  4818.4 1605.34
  4888.9 1601.05  4903.2 1598.27  4911.6 1597.53  5020.5 1597.14    5021 1596.64
  5042.8 1597.14  5051.7 1600.23  5081.9 1603.03  5122.1 1602.77  5132.2 1602.06
  5152.3 1603.37  5173.5 1603.33  5222.6  1605.5  5282.5 1606.84  5534.2 1611.54
  5544.3 1612.43  5561.9 1612.01  5634.7 1613.34  5775.5 1613.99  6107.2  1618.2
#Mann= 5 ,-1 , 0
  4477.6     .05       0  4911.6     .12       0  5020.5     .07       0
  5042.8     .12       0  5282.5     .05       0
Bank Sta=5020.5,5042.8
XS Rating Curve= 0 ,0
Exp/Cntr=0.3,0.1

Type RM Length L Ch R = 1 ,29000   ,500,500,500
BEGIN DESCRIPTION:
CHERRY SPRING CREEK 58.0
END DESCRIPTION:
XS GIS Cut Line= 3
      2730055.66     10152003.12      2730562.46     10151737.48
      2730605.68      10150903.1
#Sta/Elev= 30
  4427.8 1620.34    4436  1619.6  4441.7 1617.24  4450.4 1616.32  4480.2  1614.1
  4507.9 1613.39    4552 1607.91  4574.6 1606.56  4695.1 1602.47  4843.9 1600.48
  4856.9 1599.03  4871.6 1596.07  4910.1 1593.95  4915.7 1591.98  4993.5 1589.59
    4994 1589.09  5015.8 1589.59  5044.4    1591  5083.9  1594.9  5104.5 1598.52
  5134.5 1600.85  5154.2 1600.54  5182.1 1601.46  5284.7 1602.17    5356 1603.95
  5374.9 1603.26    5435 1603.92  5635.2 1608.64  5645.2 1607.84  5835.5 1610.79
#Mann= 5 ,-1 , 0
  4427.8     .05       0  4993.5     .05       0  5015.8     .05       0
  5083.9     .12       0  5182.1     .05       0
Bank Sta=4993.5,5015.8
XS Rating Curve= 0 ,0
Exp/Cntr=0.3,0.1

Type RM Length L Ch R = 1 ,28500   ,500,500,500
BEGIN DESCRIPTION:
CHERRY SPRING CREEK 57.0
END DESCRIPTION:
XS GIS Cut Line= 3
      2730455.71     10152103.11      2730957.08     10152015.34
      2731205.67     10151653.14
#Sta/Elev= 30
    4491 1601.31  4663.6 1597.62    4826 1596.53  4917.4 1589.08  4984.8 1581.26
  4985.3 1580.76  5008.8 1581.26  5035.9 1583.07  5073.2 1583.49  5094.2 1588.69
  5100.3  1586.1  5109.1 1588.13  5115.2 1585.84    5124 1585.96  5130.1 1588.68
  5136.1 1587.35    5145 1589.63    5151 1586.85  5159.9 1589.24  5165.9 1586.81
  5180.8 1589.29  5186.9 1587.44  5216.7 1589.85  5222.8 1588.23  5252.6 1591.35
  5258.6  1594.6  5267.5 1596.65  5309.4 1596.44    5406 1600.52  5439.3  1602.9
#Mann= 5 ,-1 , 0
    4491     .05       0  4984.8     .05       0  5008.8     .05       0
  5035.9     .12       0    5406     .05       0
Bank Sta=4984.8,5008.8
XS Rating Curve= 0 ,0
Exp/Cntr=0.3,0.1

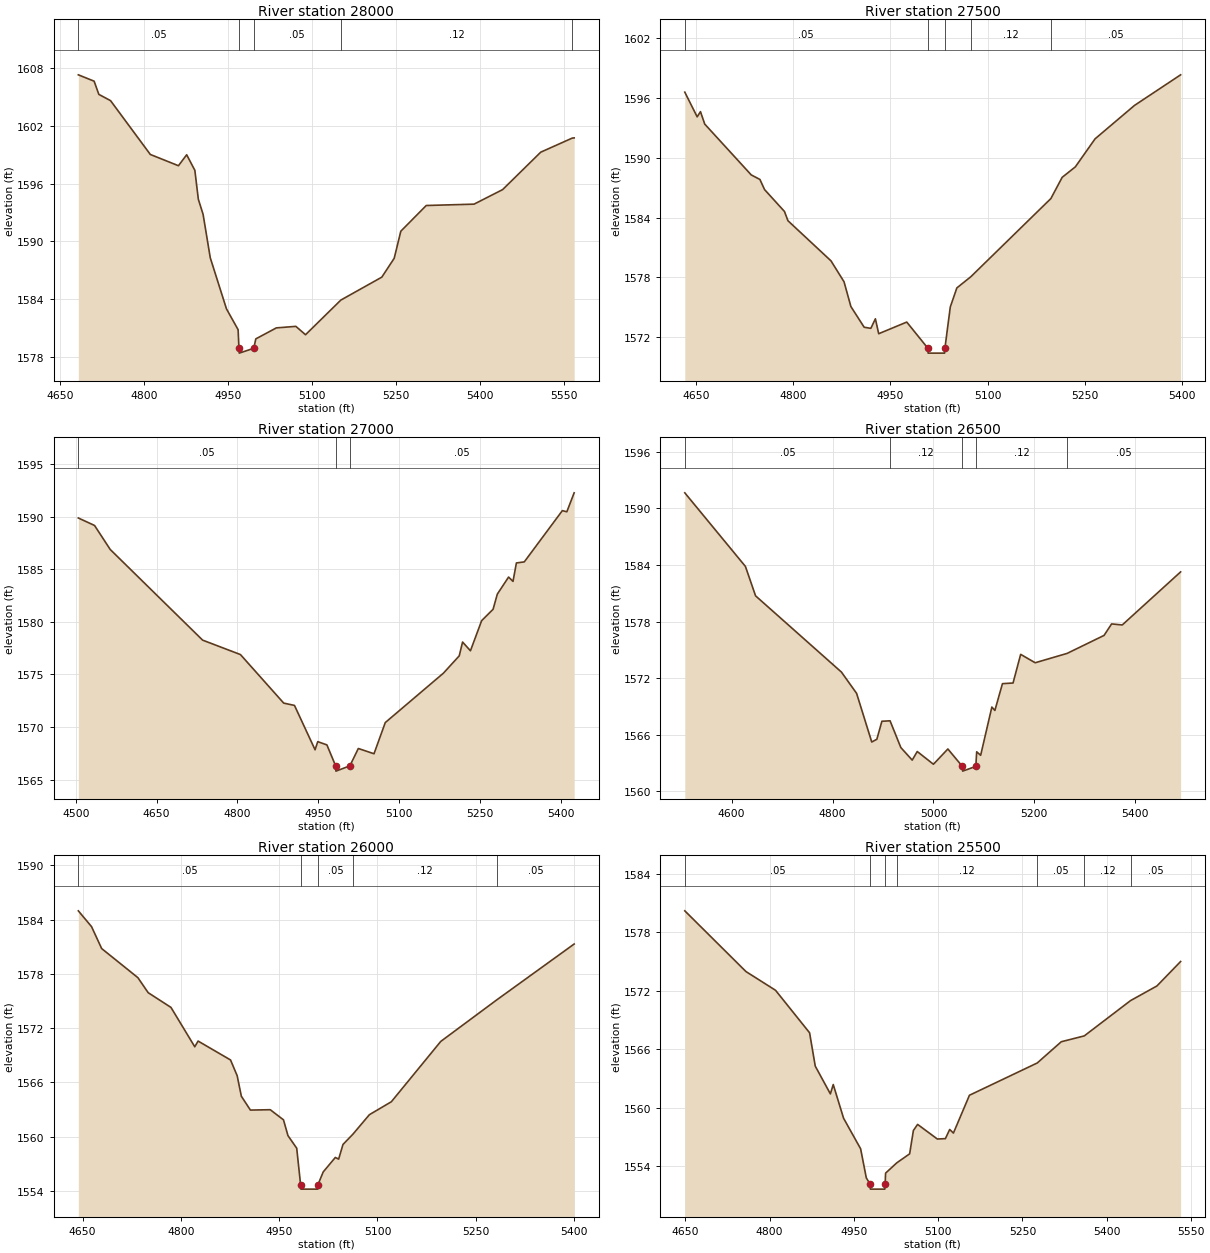
Type RM Length L Ch R = 1 ,28000   ,500,500,500
BEGIN DESCRIPTION:
CHERRY SPRING CREEK 56.0
END DESCRIPTION:
XS GIS Cut Line= 3
       2730855.7     10152753.08      2731043.27     10152496.91
      2731555.73     10152253.09
#Sta/Elev= 30
  4682.5  1607.3  4710.7 1606.64  4719.1 1605.27    4740 1604.62    4811 1599.03
  4861.2 1597.86  4875.9    1599  4890.5 1597.38  4896.7 1594.38  4905.2 1592.81
    4918  1588.3  4946.9    1583  4967.7 1580.83  4969.2  1578.9  4969.7  1578.4
  4995.6  1578.9  4999.3 1579.88  5035.9 1581.02  5070.8 1581.18    5088 1580.31
  5151.1 1583.91  5224.2 1586.29  5246.3 1588.25  5258.1 1591.06  5303.5 1593.73
  5388.8 1593.87  5439.8 1595.38  5507.9 1599.27  5564.1 1600.73  5567.5 1600.75
#Mann= 5 ,-1 , 0
  4682.5     .05       0  4969.2     .05       0  4995.6     .05       0
  5151.1     .12       0  5564.1     .05       0
Bank Sta=4969.2,4995.6
XS Rating Curve= 0 ,0
Exp/Cntr=0.3,0.1

Type RM Length L Ch R = 1 ,27500   ,500,500,500
BEGIN DESCRIPTION:
CHERRY SPRING CREEK 55.0
END DESCRIPTION:
XS GIS Cut Line= 3
      2731055.64     10152903.12      2731413.97     10152822.44
      2731805.68     10152753.11
#Sta/Elev= 30
  4632.7  1596.6  4651.8 1594.12  4656.9 1594.64  4663.5 1593.39  4735.3 1588.28
  4748.6 1587.83  4755.8 1586.81  4786.5 1584.61  4791.9 1583.68  4858.3 1579.65
  4878.4 1577.55    4889 1575.06  4909.5 1572.98  4919.8 1572.87  4926.8 1573.83
  4931.9 1572.33  4975.2  1573.5  5007.7 1570.88  5008.2 1570.38  5033.6 1570.38
  5034.1 1570.88  5042.4 1575.02  5052.5 1576.93    5074 1578.05  5197.6 1585.91
    5215 1588.04  5235.3 1589.09  5265.8 1591.91  5326.7 1595.27  5397.8 1598.34
#Mann= 5 ,-1 , 0
  4632.7     .05       0  5007.7     .05       0  5034.1     .05       0
    5074     .12       0  5197.6     .05       0
Bank Sta=5007.7,5034.1
XS Rating Curve= 0 ,0
Exp/Cntr=0.3,0.1

Type RM Length L Ch R = 1 ,27000   ,500,500,500
BEGIN DESCRIPTION:
CHERRY SPRING CREEK 54.0
END DESCRIPTION:
XS GIS Cut Line= 3
      2731055.72     10153253.11      2731549.27     10153292.27
       2731805.7      10152953.1
#Sta/Elev= 30
  4504.9 1589.86    4535 1589.15  4564.1 1586.87  4735.6 1578.26  4805.8 1576.89
  4886.1 1572.28  4906.1 1572.06  4944.3 1567.85  4949.3 1568.62  4966.3 1568.31
  4982.5 1566.32    4983 1565.82  5008.9 1566.32  5024.6 1567.97  5053.7 1567.47
  5074.6 1570.43  5182.7 1575.13  5211.9 1576.77  5218.1 1578.08  5232.7 1577.25
  5253.5 1580.11  5274.7 1581.19  5282.6 1582.63  5303.5 1584.25  5311.7 1583.84
    5318 1585.59  5332.6 1585.69  5403.3 1590.56  5411.6 1590.45  5425.2 1592.25
#Mann= 3 ,-1 , 0
  4504.9     .05       0  4982.5     .05       0  5008.9     .05       0
Bank Sta=4982.5,5008.9
XS Rating Curve= 0 ,0
Exp/Cntr=0.3,0.1

Type RM Length L Ch R = 1 ,26500   ,500,500,500
BEGIN DESCRIPTION:
CHERRY SPRING CREEK 53.0
END DESCRIPTION:
XS GIS Cut Line= 3
      2731105.66     10153753.11      2731597.73     10153781.71
       2732005.7     10154053.12
#Sta/Elev= 30
  4507.1 1591.66  4627.3 1583.85  4647.4 1580.73  4817.6 1572.64  4847.7 1570.38
  4877.7 1565.22  4887.8 1565.51  4897.8 1567.42    4914 1567.47  4935.4 1564.63
  4957.9  1563.3  4967.9 1564.21    5000 1562.86  5028.6 1564.48  5057.4 1562.63
  5057.9 1562.13    5084 1562.63  5085.7 1564.18  5093.6 1563.81  5115.8 1568.93
  5121.8 1568.57  5136.8 1571.41  5157.8 1571.48  5172.9 1574.52  5201.7 1573.63
  5264.9 1574.62  5338.2 1576.53  5353.2 1577.75  5374.3 1577.64    5490 1583.27
#Mann= 5 ,-1 , 0
  4507.1     .05       0    4914     .12       0  5057.4     .07       0
    5084     .12       0  5264.9     .05       0
Bank Sta=5057.4,5084
XS Rating Curve= 0 ,0
Exp/Cntr=0.3,0.1

Type RM Length L Ch R = 1 ,26000   ,500,500,500
BEGIN DESCRIPTION:
CHERRY SPRING CREEK 52.0
END DESCRIPTION:
XS GIS Cut Line= 3
      2731155.65     10154203.11      2731508.64       10154253.
      2731905.72     10154203.11
#Sta/Elev= 30
  4643.5 1584.96  4663.7 1583.21  4679.1 1580.79  4734.4 1577.57  4750.1 1575.91
  4784.9 1574.28  4821.2 1569.93  4826.3 1570.56  4875.8 1568.47  4885.9 1566.73
  4892.3 1564.46  4906.1 1562.93  4936.4 1562.97  4956.6 1561.85  4963.4 1560.11
  4976.8 1558.71  4982.7 1554.69  4983.2 1554.19  5008.8 1554.19  5009.3 1554.69
  5017.2 1556.09  5035.7 1557.69  5040.8 1557.51  5047.4 1559.13  5062.5 1560.26
  5087.7 1562.42  5121.2 1563.85  5196.6 1570.52  5282.4 1575.13  5400.2 1581.29
#Mann= 5 ,-1 , 0
  4643.5     .05       0  4982.7     .05       0  5009.3     .05       0
  5062.5     .12       0  5282.4     .05       0
Bank Sta=4982.7,5009.3
XS Rating Curve= 0 ,0
Exp/Cntr=0.3,0.1

Type RM Length L Ch R = 1 ,25500   ,500,500,500
BEGIN DESCRIPTION:
CHERRY SPRING CREEK 51.0
END DESCRIPTION:
XS GIS Cut Line= 3
      2731155.72     10154703.12      2731503.25     10154750.18
      2731905.67     10154403.13
#Sta/Elev= 30
  4649.3 1580.18  4758.1 1573.95  4810.7 1572.03  4871.3 1567.67  4881.4 1564.25
  4908.3  1561.4  4913.4 1562.36  4931.8  1558.9  4962.1 1555.77  4972.2 1552.79
    4979 1552.13  4979.5 1551.63  5005.2 1551.63  5005.7 1552.13  5006.5 1553.27
  5026.5 1554.33  5049.3 1555.25    5056 1557.65  5063.5 1558.27  5098.6 1556.77
  5112.9 1556.81  5120.6 1557.75  5127.2 1557.38  5155.7 1561.26  5276.3 1564.57
  5319.1 1566.75    5360 1567.35  5442.3 1570.97  5489.2 1572.47  5531.4 1574.98
#Mann= 7 ,-1 , 0
  4649.3     .05       0    4979     .05       0  5005.7     .05       0
  5026.5     .12       0  5276.3     .05       0    5360     .12       0
  5442.3     .05       0
Bank Sta=4979,5005.7
XS Rating Curve= 0 ,0
Exp/Cntr=0.3,0.1

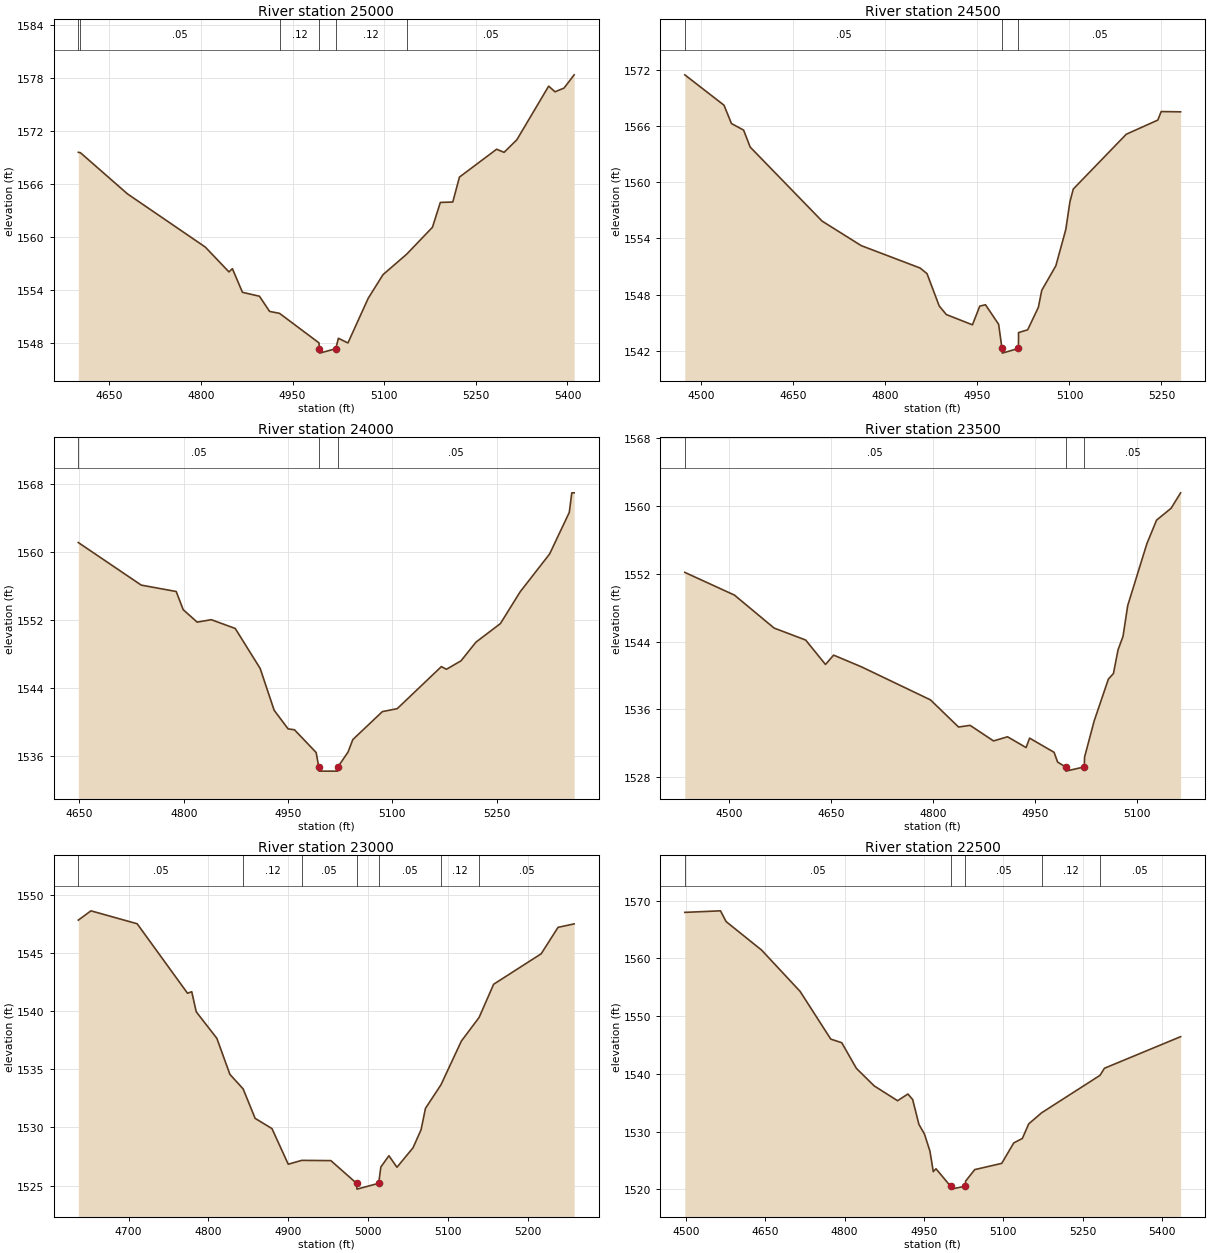
Type RM Length L Ch R = 1 ,25000   ,500,500,500
BEGIN DESCRIPTION:
CHERRY SPRING CREEK 50.0
END DESCRIPTION:
XS GIS Cut Line= 3
      2731255.64     10155053.09      2731611.63      10155236.6
      2732005.67     10155353.11
#Sta/Elev= 30
  4599.5 1569.62  4602.9 1569.58  4679.9 1564.92  4807.3  1558.9    4846 1556.09
  4851.6 1556.46  4868.1 1553.78  4895.9 1553.34  4912.5 1551.62  4928.8  1551.4
  4993.3 1548.06    4994  1547.4  4994.5  1546.9  5020.8  1547.4  5025.1 1548.58
  5040.7 1548.05  5073.9 1553.11  5098.1 1555.78  5136.6 1558.08    5179 1561.14
  5191.9 1563.95  5212.3    1564  5223.2 1566.82    5284 1569.97  5296.2 1569.62
  5317.1 1571.04  5369.2 1577.11  5379.6 1576.47  5394.3 1576.89  5410.9 1578.39
#Mann= 6 ,-1 , 0
  4599.5     .12       0  4602.9     .05       0  4928.8     .12       0
    4994     .07       0  5020.8     .12       0  5136.6     .05       0
Bank Sta=4994,5020.8
XS Rating Curve= 0 ,0
Exp/Cntr=0.3,0.1

Type RM Length L Ch R = 1 ,24500   ,500,500,500
BEGIN DESCRIPTION:
CHERRY SPRING CREEK 49.0
END DESCRIPTION:
XS GIS Cut Line= 3
      2731205.69     10155153.14      2731388.04     10155647.69
      2731505.68      10155903.1
#Sta/Elev= 30
  4472.9 1571.45  4536.8 1568.21    4549 1566.25  4568.8 1565.55  4579.5 1563.74
  4696.7 1555.84  4760.6 1553.22  4856.6 1550.83  4867.8 1550.23  4887.6 1546.79
  4899.2 1545.87  4941.8 1544.77  4953.8 1546.77  4963.1 1546.91  4984.5 1544.83
    4990 1542.25  4990.5 1541.75  5016.8 1542.25    5017 1543.94  5031.9 1544.24
  5049.3 1546.64  5054.8 1548.45  5077.8 1551.07    5094 1554.94  5100.7 1557.89
  5106.2 1559.26  5192.6 1565.11    5244 1566.62  5249.5 1567.53  5281.2  1567.5
#Mann= 3 ,-1 , 0
  4472.9     .05       0    4990     .05       0  5016.8     .05       0
Bank Sta=4990,5016.8
XS Rating Curve= 0 ,0
Exp/Cntr=0.3,0.1

Type RM Length L Ch R = 1 ,24000   ,500,500,500
BEGIN DESCRIPTION:
CHERRY SPRING CREEK 48.0
END DESCRIPTION:
XS GIS Cut Line= 3
      2730655.71     10155903.11      2731005.13     10155942.19
      2731255.65     10156203.08
#Sta/Elev= 30
  4648.4 1561.12  4738.9 1556.12  4789.2 1555.37  4799.3 1553.23  4819.4 1551.77
  4839.6 1552.06  4874.1 1551.03    4910 1546.33  4930.1 1541.42  4950.2 1539.23
  4959.3 1539.13  4990.5 1536.46  4994.3 1534.77  4994.8 1534.27  5021.4 1534.27
  5021.9 1534.77  5036.4 1536.51  5043.3 1537.98  5085.8 1541.26  5107.2 1541.61
  5170.7 1546.55  5177.9 1546.23    5199 1547.23  5220.4 1549.42  5255.6  1551.6
  5283.9 1555.32  5326.4 1559.78  5354.7 1564.66  5358.3 1566.96  5361.7 1566.96
#Mann= 3 ,-1 , 0
  4648.4     .05       0  4994.3     .05       0  5021.9     .05       0
Bank Sta=4994.3,5021.9
XS Rating Curve= 0 ,0
Exp/Cntr=0.3,0.1

Type RM Length L Ch R = 1 ,23500   ,500,500,500
BEGIN DESCRIPTION:
CHERRY SPRING CREEK 47.0
END DESCRIPTION:
XS GIS Cut Line= 3
      2730394.76     10156295.79      2730943.15     10156433.01
       2731055.7     10156553.12
#Sta/Elev= 30
  4434.7 1552.16  4507.8 1549.48  4566.2 1545.59  4612.6 1544.18  4641.8  1541.3
  4653.8  1542.4    4695 1541.01  4796.4 1537.12  4837.7 1533.92  4854.7 1534.12
  4889.2 1532.28  4909.8 1532.77  4937.1  1531.5  4942.3 1532.61  4978.3 1530.94
  4983.5 1529.79  4995.2 1529.22  4995.7 1528.72  5022.8 1529.22  5023.2 1530.37
  5037.3 1534.63  5058.3 1539.58  5065.7 1540.23  5072.5 1543.03  5079.8 1544.61
  5086.7 1548.24    5115 1555.56  5129.2 1558.32  5150.6 1559.72  5164.6 1561.54
#Mann= 3 ,-1 , 0
  4434.7     .05       0  4995.2     .05       0  5022.8     .05       0
Bank Sta=4995.2,5022.8
XS Rating Curve= 0 ,0
Exp/Cntr=0.3,0.1

Type RM Length L Ch R = 1 ,23000   ,500,500,500
BEGIN DESCRIPTION:
CHERRY SPRING CREEK 46.0
END DESCRIPTION:
XS GIS Cut Line= 3
      2730405.65     10157003.12      2730749.75     10156887.85
       2731005.7     10156853.11
#Sta/Elev= 30
  4637.1 1547.81  4652.9 1548.61  4710.8  1547.5  4773.9 1541.53  4779.2 1541.66
  4784.8 1539.94  4810.7 1537.65    4827 1534.56  4843.6 1533.31  4858.6 1530.78
  4879.7  1529.9  4900.1 1526.84  4916.9 1527.17  4953.5 1527.15  4985.7  1525.2
  4986.2  1524.7  5013.4  1525.2  5016.1  1526.6  5026.2 1527.57  5036.3 1526.58
  5056.4 1528.25  5066.5  1529.8    5072 1531.64  5091.4 1533.66    5117 1537.42
  5139.2 1539.45  5157.4  1542.3    5217 1544.92  5238.1 1547.19  5258.3 1547.49
#Mann= 7 ,-1 , 0
  4637.1     .05       0  4843.6     .12       0  4916.9     .05       0
  4985.7     .05       0  5013.4     .05       0  5091.4     .12       0
  5139.2     .05       0
Bank Sta=4985.7,5013.4
XS Rating Curve= 0 ,0
Exp/Cntr=0.3,0.1

Type RM Length L Ch R = 1 ,22500   ,500,500,500
BEGIN DESCRIPTION:
CHERRY SPRING CREEK 45.0
END DESCRIPTION:
XS GIS Cut Line= 3
      2730130.69     10157478.11      2730612.86     10157339.48
      2731005.69     10157153.11
#Sta/Elev= 30
  4498.3 1567.97  4565.7 1568.24  4576.3 1566.38  4643.5 1561.43  4716.1 1554.29
    4774 1546.03  4794.8  1545.4  4822.4 1540.96  4856.1 1537.92  4900.2 1535.36
  4919.7 1536.52  4928.7 1535.56  4940.5 1531.26  4950.9 1529.61  4961.3 1526.64
  4967.6 1523.08  4972.8 1523.57  5000.3 1520.55  5000.8 1520.05    5028 1520.55
  5028.7 1521.43  5045.9 1523.43  5096.9 1524.51  5119.6 1528.05  5135.9 1528.83
  5147.9 1531.35  5172.3 1533.27  5282.5 1539.75  5290.9 1540.98  5434.8 1546.45
#Mann= 5 ,-1 , 0
  4498.3     .05       0  5000.3     .03       0    5028     .05       0
  5172.3     .12       0  5282.5     .05       0
Bank Sta=5000.3,5028
XS Rating Curve= 0 ,0
Exp/Cntr=0.3,0.1

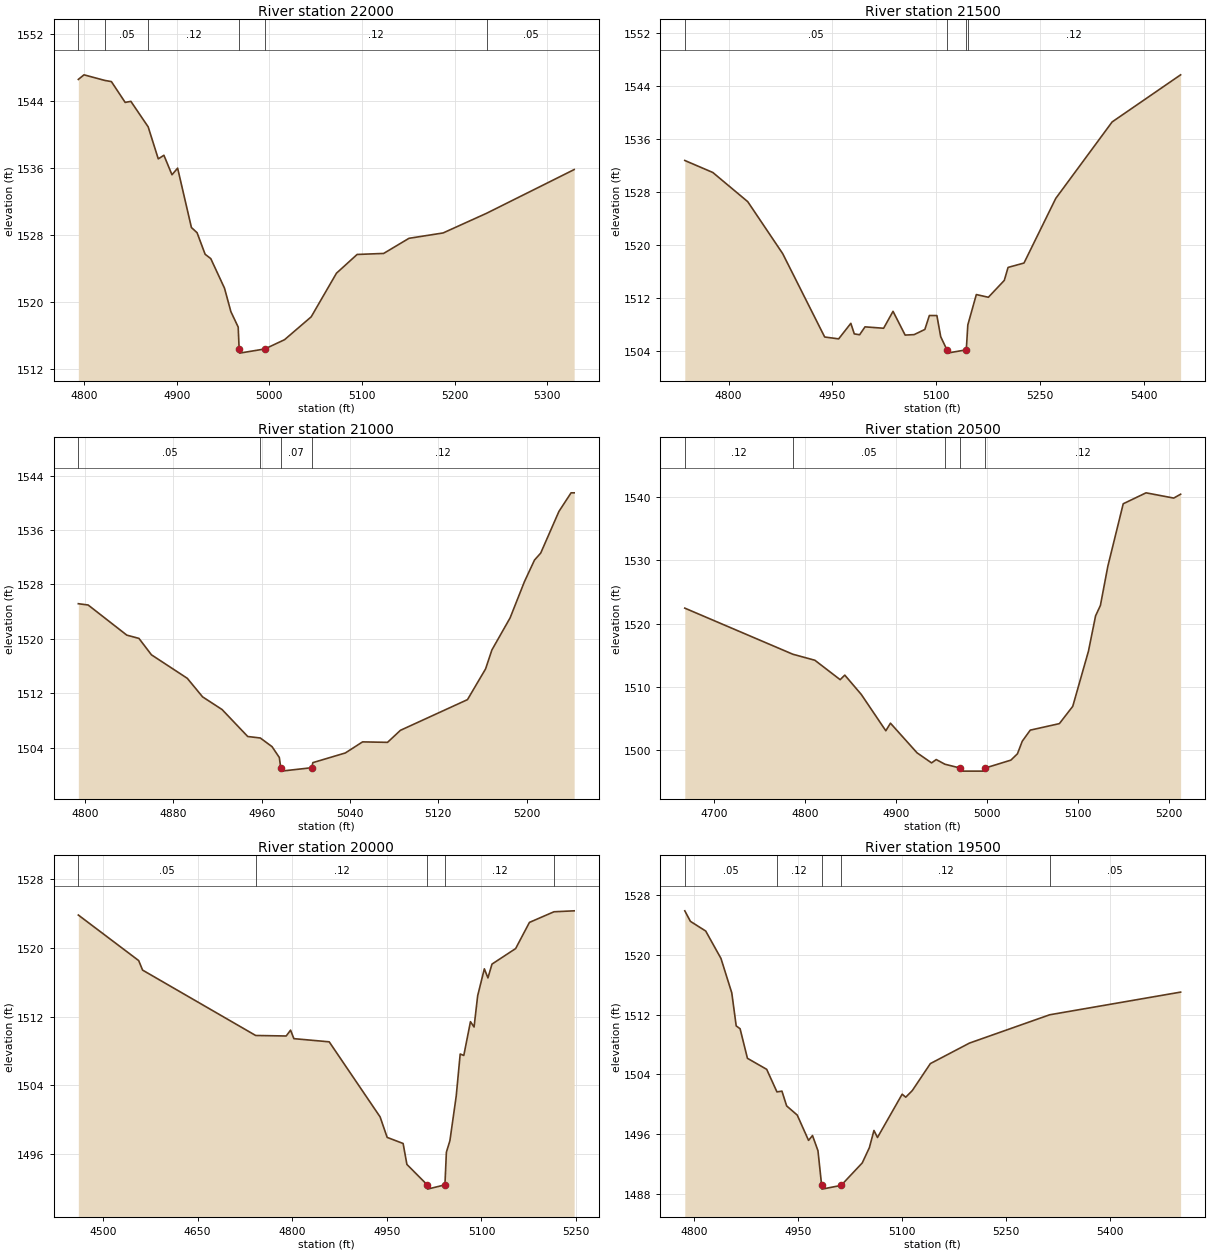
Type RM Length L Ch R = 1 ,22000   ,500,500,500
BEGIN DESCRIPTION:
CHERRY SPRING CREEK 44.0
END DESCRIPTION:
XS GIS Cut Line= 3
      2730680.69      10157878.1      2730849.74     10157759.85
      2731105.67     10157553.12
#Sta/Elev= 30
  4793.7 1546.59  4799.8 1547.14  4822.3 1546.47  4829.4 1546.33  4844.3 1543.84
  4850.4 1543.97  4869.1 1540.92    4880 1537.09  4886.1 1537.52  4894.8 1535.19
  4900.9 1535.98  4915.8 1528.88  4921.9 1528.26  4930.6 1525.68  4936.7 1525.16
  4951.5 1521.63  4958.4 1518.82  4966.3 1516.97  4967.3 1514.36  4967.8 1513.86
  4995.1 1514.36  5016.4 1515.47  5045.1  1518.2  5072.4 1523.42  5094.7 1525.66
  5123.3 1525.78  5150.7 1527.59  5187.5 1528.23  5234.6 1530.59    5329 1535.81
#Mann= 6 ,-1 , 0
  4793.7     .12       0  4822.3     .05       0  4869.1     .12       0
  4967.3     .07       0  4995.1     .12       0  5234.6     .05       0
Bank Sta=4967.3,4995.1
XS Rating Curve= 0 ,0
Exp/Cntr=0.3,0.1

Type RM Length L Ch R = 1 ,21500   ,500,500,500
BEGIN DESCRIPTION:
CHERRY SPRING CREEK 43.0
END DESCRIPTION:
XS GIS Cut Line= 3
      2731155.68     10158353.16      2731193.68     10158092.72
      2731605.65     10157903.13
#Sta/Elev= 30
  4736.8 1532.78  4777.3 1530.97  4827.8 1526.57  4878.3 1518.74    4939 1506.17
  4959.2 1505.89  4976.8 1508.23  4981.8 1506.64  4989.5 1506.51  4997.3  1507.7
  5024.2 1507.49  5037.8 1510.04  5055.3 1506.46  5068.3 1506.53  5083.8 1507.31
  5090.3 1509.41  5101.2  1509.4  5106.7 1506.22  5115.7 1504.24  5116.2 1503.74
  5143.7 1504.24  5145.9 1507.99  5158.2 1512.57  5175.6 1512.16  5198.6  1514.7
  5204.1 1516.66  5227.1 1517.32    5273 1527.06  5354.5 1538.59  5453.5 1545.69
#Mann= 4 ,-1 , 0
  4736.8     .05       0  5115.7     .05       0  5143.7     .05       0
  5145.9     .12       0
Bank Sta=5115.7,5143.7
XS Rating Curve= 0 ,0
Exp/Cntr=0.3,0.1

Type RM Length L Ch R = 1 ,21000   ,500,500,500
BEGIN DESCRIPTION:
CHERRY SPRING CREEK 42.0
END DESCRIPTION:
XS GIS Cut Line= 3
      2731355.65     10158503.13      2731543.58     10158418.76
      2731655.66     10158203.16
#Sta/Elev= 30
    4794 1525.16  4802.9 1524.97  4837.9 1520.54  4848.9 1520.06  4860.2 1517.65
  4892.7 1514.19  4906.5 1511.47  4924.2  1509.6  4947.4 1505.64  4958.8 1505.42
  4969.4 1504.15    4976 1502.56  4977.3 1501.05  4977.8 1500.55  5005.3 1501.05
  5006.4  1501.8  5035.8 1503.22  5051.4 1504.85    5074 1504.78  5085.7 1506.55
  5146.4 1511.06  5162.8 1515.58  5168.5 1518.36    5185 1523.08    5198 1528.41
  5207.1 1531.58  5212.7  1532.6  5229.2 1538.72  5240.2 1541.46    5243 1541.46
#Mann= 4 ,-1 , 0
    4794     .05       0  4958.8     .12       0  4977.3     .07       0
  5005.3     .12       0
Bank Sta=4977.3,5005.3
XS Rating Curve= 0 ,0
Exp/Cntr=0.3,0.1

Type RM Length L Ch R = 1 ,20500   ,500,500,500
BEGIN DESCRIPTION:
CHERRY SPRING CREEK 41.0
END DESCRIPTION:
XS GIS Cut Line= 3
      2731505.67     10158753.11       2731831.1     10158820.32
       2732030.7     10158746.55
#Sta/Elev= 30
  4667.7 1522.46  4786.5 1515.17  4810.7 1514.22  4838.5 1511.15  4843.6 1511.87
  4861.7 1508.82  4888.7 1503.07  4893.8 1504.27    4923 1499.59    4939 1497.99
  4944.1 1498.52  4953.7 1497.78  4970.1 1497.19  4970.6 1496.69  4997.7 1496.69
  4998.2 1497.19  5026.2 1498.43  5033.4 1499.43  5038.7 1501.42  5047.5 1503.17
  5079.5  1504.2  5094.2 1506.93  5111.5 1515.67  5119.3 1521.24  5124.6 1522.88
  5132.8 1529.09  5149.7 1538.96  5174.8 1540.69  5205.2 1539.86  5212.8 1540.47
#Mann= 5 ,-1 , 0
  4667.7     .12       0  4786.5     .05       0  4953.7     .12       0
  4970.1     .07       0  4998.2     .12       0
Bank Sta=4970.1,4998.2
XS Rating Curve= 0 ,0
Exp/Cntr=0.3,0.1

Type RM Length L Ch R = 1 ,20000   ,500,500,500
BEGIN DESCRIPTION:
CHERRY SPRING CREEK 40.0
END DESCRIPTION:
XS GIS Cut Line= 3
      2731405.72     10159103.12      2731912.75     10159286.58
       2732130.7     10159402.81
#Sta/Elev= 30
  4460.8 1523.85  4556.5 1518.54  4562.7 1517.43    4742 1509.81  4790.4 1509.75
  4797.3 1510.43  4802.6 1509.44  4858.6 1509.07  4939.3 1500.32  4950.5 1497.93
  4975.8 1497.22  4981.8 1494.78    5014  1492.4  5014.5  1491.9  5042.1  1492.4
  5044.4  1496.2    5050 1497.55    5060 1502.75  5066.3 1507.65    5072 1507.48
  5082.6 1511.42  5088.3  1510.8    5094 1514.44  5104.6 1517.58  5110.3 1516.52
  5116.7 1518.13  5154.2 1519.94  5176.1 1522.99    5215 1524.23    5247 1524.34
#Mann= 5 ,-1 , 0
  4460.8     .05       0    4742     .12       0    5014     .07       0
  5042.1     .12       0    5215     .05       0
Bank Sta=5014,5042.1
XS Rating Curve= 0 ,0
Exp/Cntr=0.3,0.1

Type RM Length L Ch R = 1 ,19500   ,500,500,500
BEGIN DESCRIPTION:
CHERRY SPRING CREEK 39.0
END DESCRIPTION:
XS GIS Cut Line= 3
      2731455.72     10159803.09      2731644.86     10159703.21
      2732130.72      10159578.1
#Sta/Elev= 30
  4786.1 1525.91  4794.2  1524.5  4816.3  1523.2  4838.3 1519.53  4853.9 1514.92
  4860.3 1510.49  4865.9 1510.11  4876.5 1506.15  4904.3 1504.67  4919.1 1501.65
  4926.3 1501.75  4933.1 1499.77  4948.4 1498.54  4964.7 1495.15  4970.4  1495.8
  4978.3 1493.77  4983.6 1489.12  4984.1 1488.62  5011.7 1489.12  5042.2 1492.13
  5052.5 1494.18  5059.1 1496.48  5064.2 1495.54  5099.8 1501.34    5105 1500.94
  5114.4 1501.82  5140.5 1505.44    5197 1508.19  5312.7 1511.98  5501.7 1515.02
#Mann= 5 ,-1 , 0
  4786.1     .05       0  4919.1     .12       0  4983.6     .07       0
  5011.7     .12       0  5312.7     .05       0
Bank Sta=4983.6,5011.7
XS Rating Curve= 0 ,0
Exp/Cntr=0.3,0.1