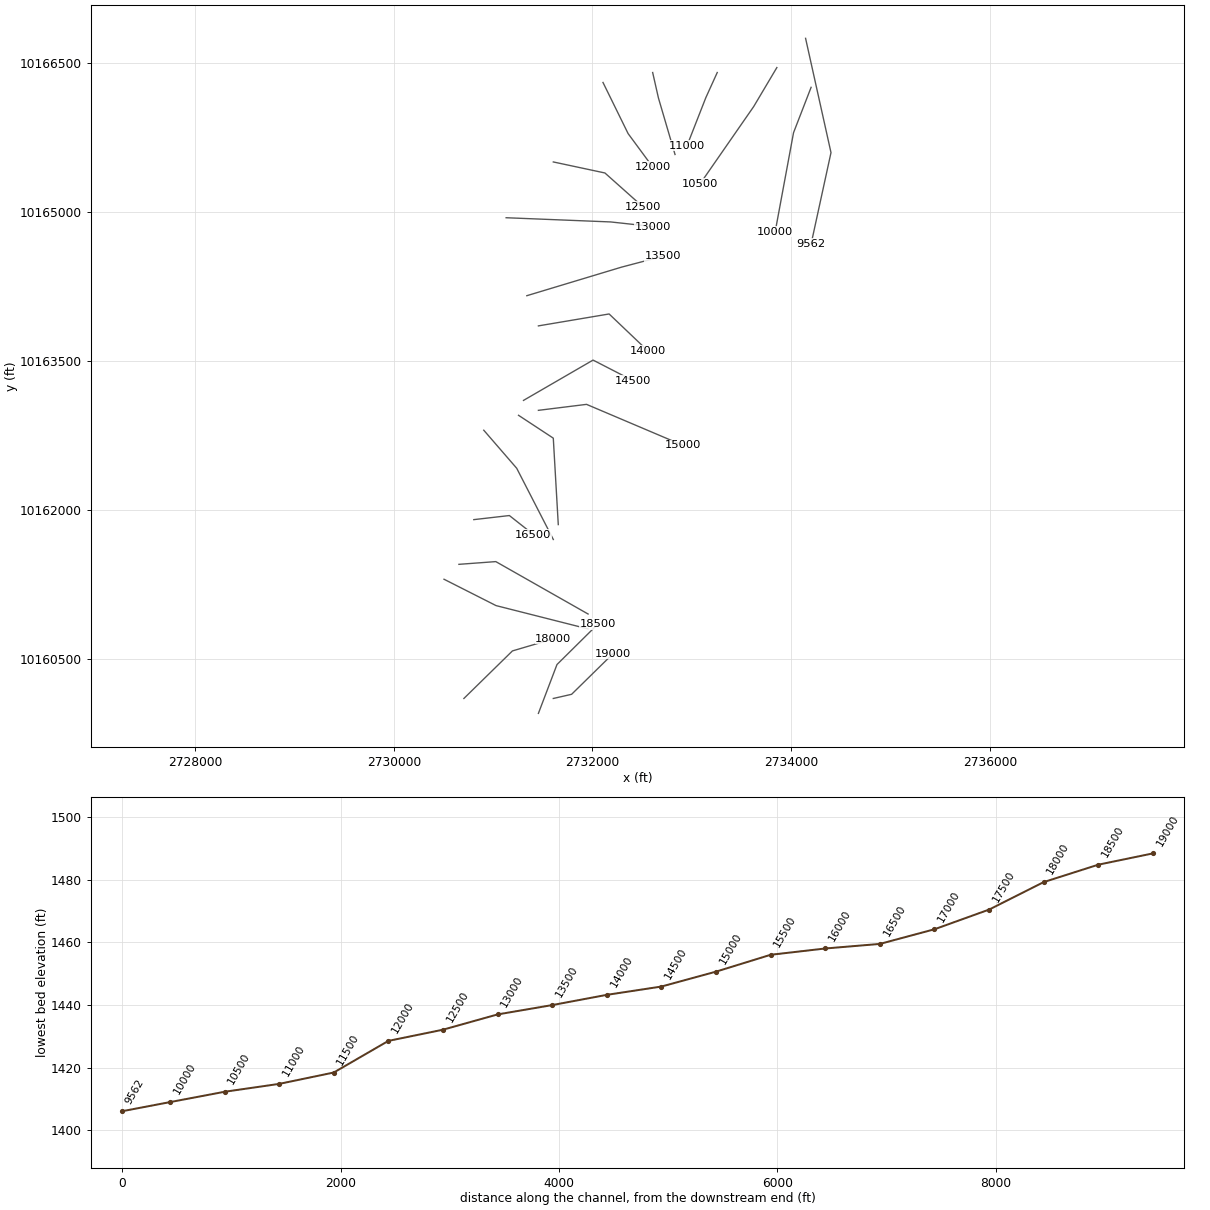
HEC-RAS study CHERRY SPRING CREEK.prj: CHERRY SPRING CREEK Base Level Engineering

--- CHERRY SPRING CREEK.g01 (geometry) --- (continued)

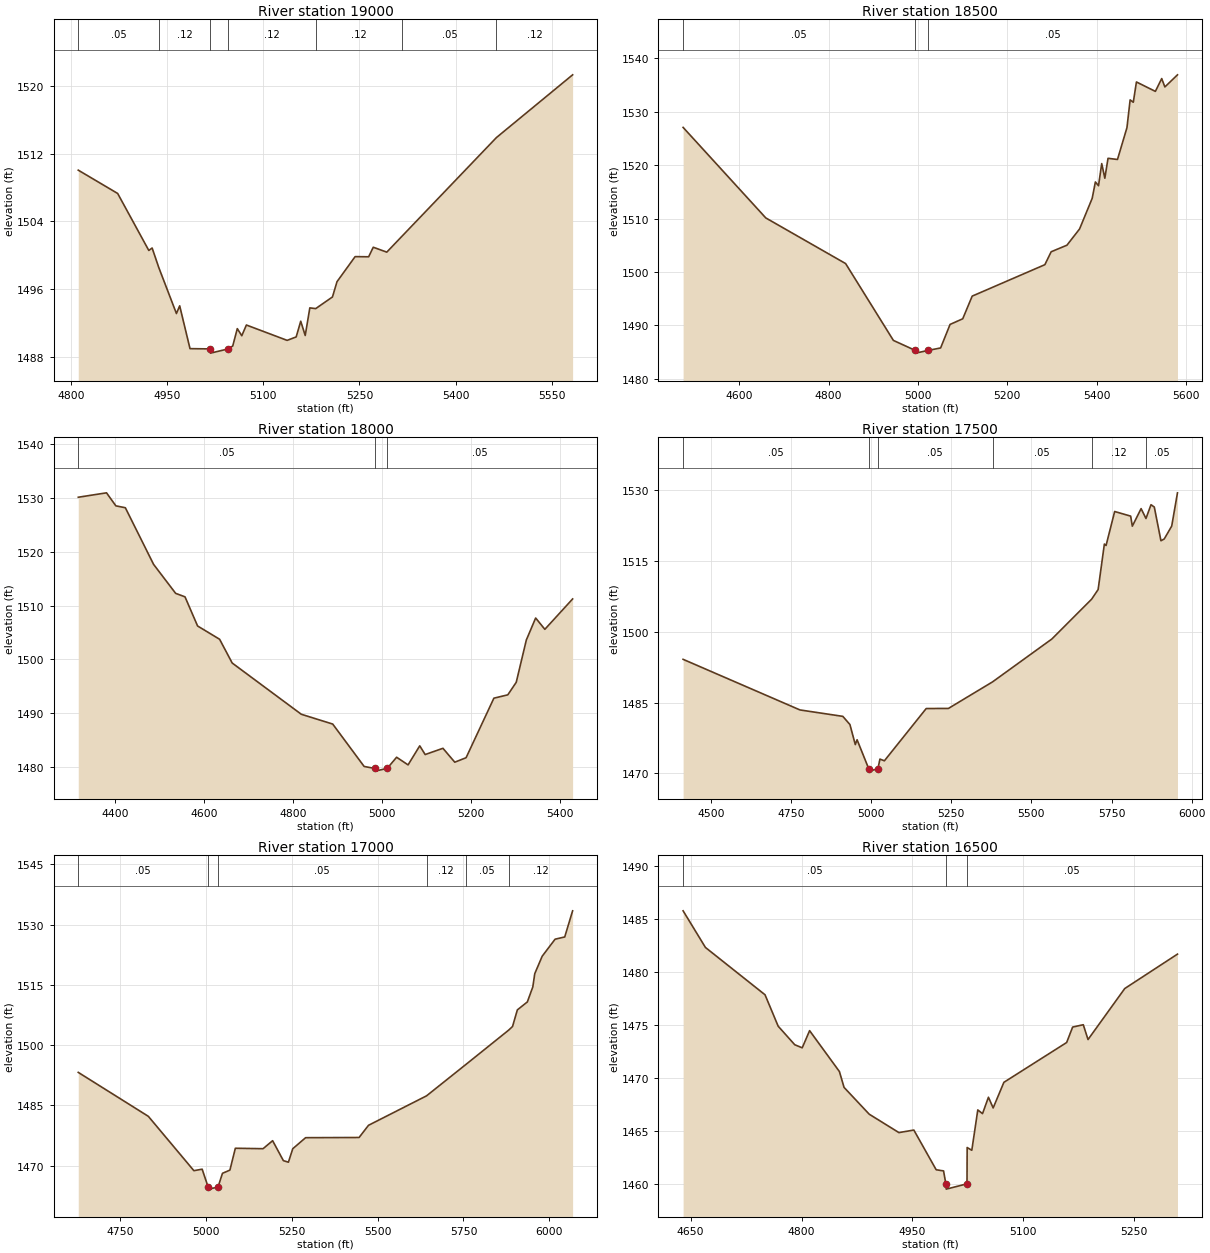
Type RM Length L Ch R = 1 ,19000   ,500,500,500
BEGIN DESCRIPTION:
CHERRY SPRING CREEK 38.0
END DESCRIPTION:
XS GIS Cut Line= 3
      2731605.68     10160103.11      2731789.87     10160145.06
      2732205.69     10160553.12
#Sta/Elev= 30
  4811.1 1510.07  4872.6 1507.31  4921.2 1500.56  4926.4 1500.85  4936.8 1498.53
  4964.3 1493.09  4969.4    1494  4985.5 1488.93    5017  1488.9  5017.5  1488.4
  5045.1  1488.9  5052.2 1489.25  5059.3  1491.3  5066.3 1490.46  5073.5 1491.73
  5137.1 1489.91  5151.2 1490.32  5158.3 1492.18  5165.3 1490.49  5172.5 1493.76
  5181.6 1493.67  5207.8 1495.05  5214.9 1496.86  5243.2 1499.83  5264.3 1499.81
  5271.5 1500.94  5292.6 1500.36  5316.9 1502.29  5463.7 1513.93  5582.6 1521.36
#Mann= 7 ,-1 , 0
  4811.1     .05       0  4936.8     .12       0    5017     .07       0
  5045.1     .12       0  5181.6     .12       0  5316.9     .05       0
  5463.7     .12       0
Bank Sta=5017,5045.1
XS Rating Curve= 0 ,0
Exp/Cntr=0.3,0.1

Type RM Length L Ch R = 1 ,18500   ,500,500,500
BEGIN DESCRIPTION:
CHERRY SPRING CREEK 37.0
END DESCRIPTION:
XS GIS Cut Line= 3
      2731455.67     10159953.08      2731642.56     10160444.54
      2732055.66     10160853.09
#Sta/Elev= 30
  4474.2 1527.09  4659.3 1510.13    4838 1501.58    4945 1487.18  4994.2  1485.3
  4994.7  1484.8  5022.3  1485.3  5050.7 1485.77  5071.9 1490.18  5100.2 1491.23
  5121.4 1495.48  5284.1 1501.37  5298.2 1503.79  5333.5 1505.02  5361.8 1508.06
  5390.1 1513.81  5397.2 1516.87  5404.2 1516.16  5411.4 1520.31  5418.4 1517.57
  5425.5  1521.3  5446.7 1521.08  5467.9 1527.05    5475 1532.24  5482.1  1531.8
  5489.1  1535.6  5531.5 1533.84  5545.7 1536.24  5552.8 1534.67    5581 1536.94
#Mann= 3 ,-1 , 0
  4474.2     .05       0  4994.2     .05       0  5022.3     .05       0
Bank Sta=4994.2,5022.3
XS Rating Curve= 0 ,0
Exp/Cntr=0.3,0.1

Type RM Length L Ch R = 1 ,18000   ,500,500,500
BEGIN DESCRIPTION:
CHERRY SPRING CREEK 36.0
END DESCRIPTION:
XS GIS Cut Line= 3
      2730705.72     10160103.15      2731194.12     10160581.59
      2731605.66      10160703.1
#Sta/Elev= 30
  4316.3 1530.11  4379.9 1530.93    4401 1528.51  4422.3 1528.16  4485.9 1517.64
  4535.5 1512.26  4556.6 1511.61  4584.9  1506.2  4634.5 1503.73  4662.8 1499.32
  4818.4  1489.8  4889.1 1487.98  4959.8 1480.11  4983.5 1479.74    4984 1479.24
  5011.7 1479.74  5032.9 1481.82  5058.7  1480.4    5085 1483.94  5097.2 1482.32
  5137.2 1483.48  5163.8  1480.9  5189.3 1481.73  5251.9 1492.79  5283.2 1493.41
  5302.2 1495.74  5324.9 1503.59  5345.9 1507.68  5366.6 1505.58  5429.1 1511.22
#Mann= 3 ,-1 , 0
  4316.3     .05       0  4983.5     .05       0  5011.7     .05       0
Bank Sta=4983.5,5011.7
XS Rating Curve= 0 ,0
Exp/Cntr=0.3,0.1

Type RM Length L Ch R = 1 ,17500   ,500,500,500
BEGIN DESCRIPTION:
CHERRY SPRING CREEK 35.0
END DESCRIPTION:
XS GIS Cut Line= 3
      2730505.67     10161303.12       2731029.2     10161037.85
      2731955.72      10160803.1
#Sta/Elev= 30
  4413.1 1494.16  4777.8 1483.43  4911.5 1482.07  4933.7 1480.33  4950.4 1476.09
    4956 1477.11  4992.4 1470.96  4992.9 1470.46    5021 1470.96  5027.3 1473.01
  5041.2 1472.65  5171.7 1483.73    5241 1483.75  5378.9 1489.39  5563.8 1498.47
  5687.9 1506.91  5708.2 1508.96  5727.7  1518.6  5732.9 1518.29  5759.8  1525.5
  5809.7 1524.52  5814.9 1522.39  5842.3 1526.11  5857.5 1524.02  5873.2 1526.94
  5883.5 1526.44  5904.2  1519.3  5914.5 1519.68  5937.8 1522.41  5955.8 1529.46
#Mann= 6 ,-1 , 0
  4413.1     .05       0  4992.4     .05       0    5021     .05       0
  5378.9     .05       0  5687.9     .12       0  5857.5     .05       0
Bank Sta=4992.4,5021
XS Rating Curve= 0 ,0
Exp/Cntr=0.3,0.1

Type RM Length L Ch R = 1 ,17000   ,500,500,500
BEGIN DESCRIPTION:
CHERRY SPRING CREEK 34.0
END DESCRIPTION:
XS GIS Cut Line= 3
      2730655.72     10161453.11       2731026.9     10161480.65
      2731955.65     10160953.13
#Sta/Elev= 30
  4627.8 1493.23  4831.9  1482.3  4964.7 1468.77  4988.8 1469.14  5006.3 1464.68
  5006.8 1464.18  5034.9 1464.68    5048 1468.12  5069.6 1468.91  5085.5 1474.35
  5166.2 1474.24  5194.1 1476.23  5225.4 1471.27  5240.1 1470.88  5252.7 1474.23
  5290.2 1476.98    5446 1477.03  5473.4 1480.06  5642.5 1487.39  5757.6 1495.23
  5881.3 1503.71    5893 1504.64  5907.1 1508.78  5936.2 1510.76  5952.1 1514.49
  5957.8 1517.79  5979.5 1522.14    6017 1526.37  6045.1 1526.93  6068.1 1533.43
#Mann= 6 ,-1 , 0
  4627.8     .05       0  5006.3     .05       0  5034.9     .05       0
  5642.5     .12       0  5757.6     .05       0  5881.3     .12       0
Bank Sta=5006.3,5034.9
XS Rating Curve= 0 ,0
Exp/Cntr=0.3,0.1

Type RM Length L Ch R = 1 ,16500   ,500,500,500
BEGIN DESCRIPTION:
CHERRY SPRING CREEK 33.0
END DESCRIPTION:
XS GIS Cut Line= 3
      2730805.66     10161903.11       2731163.5     10161944.24
      2731405.67     10161753.12
#Sta/Elev= 30
  4639.8 1485.79    4670 1482.33  4750.6 1477.86  4768.4 1474.89  4790.8 1473.14
  4800.9 1472.85  4810.9 1474.47  4851.2 1470.61  4857.5 1469.11  4891.5 1466.58
  4931.7 1464.84  4951.9 1465.08  4982.1 1461.33  4992.1 1461.22  4995.2    1460
  4995.7  1459.5  5023.8    1460    5024 1463.43  5030.3 1463.17  5038.4 1466.98
  5044.8 1466.63  5052.8 1468.18  5059.2 1467.17  5073.7 1469.59  5158.6 1473.35
  5166.7 1474.81  5181.1 1475.03  5187.5 1473.63  5237.2 1478.45  5308.5  1481.7
#Mann= 3 ,-1 , 0
  4639.8     .05       0  4995.2     .05       0  5023.8     .05       0
Bank Sta=4995.2,5023.8
XS Rating Curve= 0 ,0
Exp/Cntr=0.3,0.1

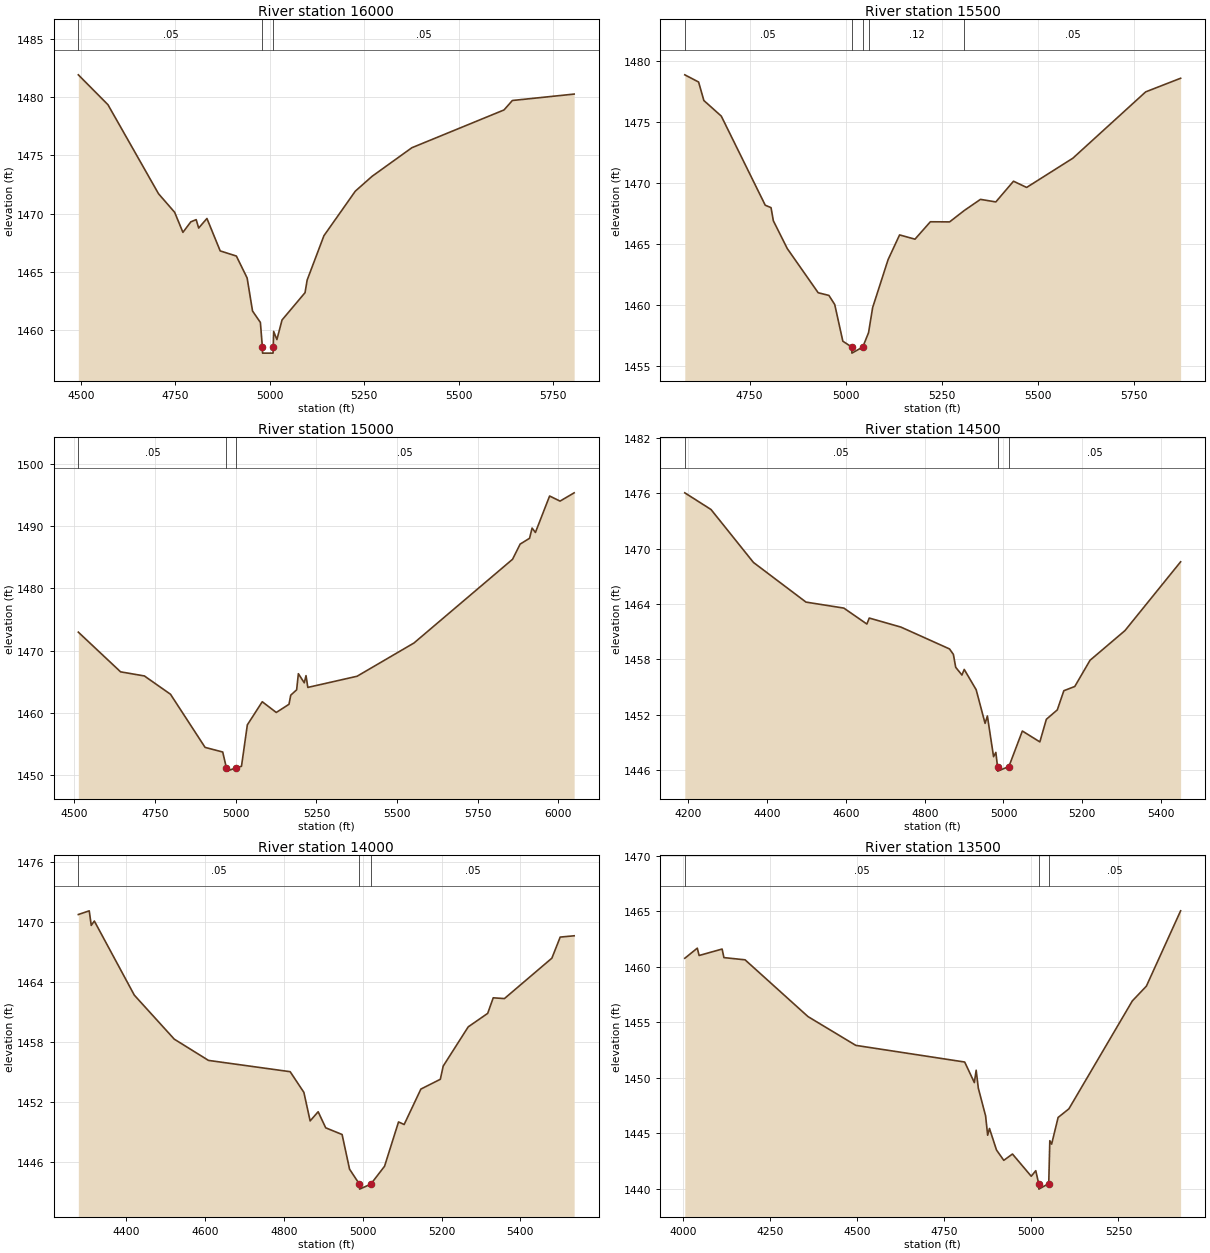
Type RM Length L Ch R = 1 ,16000   ,500,500,500
BEGIN DESCRIPTION:
CHERRY SPRING CREEK 32.0
END DESCRIPTION:
XS GIS Cut Line= 3
      2730905.68     10162803.11      2731237.36     10162419.92
      2731605.68     10161703.11
#Sta/Elev= 30
  4493.2 1481.89  4571.6 1479.33  4705.5  1471.7  4748.2 1470.11  4770.1 1468.39
    4791 1469.29  4805.2 1469.48  4811.8 1468.76  4833.7 1469.58  4868.8  1466.8
  4911.6 1466.36  4940.1 1464.48  4954.4 1461.65  4975.2 1460.67  4980.5 1458.54
    4981 1458.04  5008.7 1458.04  5009.2 1458.54  5010.3  1459.9  5018.9  1459.2
  5032.5 1460.88  5093.4 1463.22    5099  1464.3  5143.4  1468.1  5226.5 1471.92
  5270.8 1473.19  5376.1 1475.64  5620.2 1478.88  5642.3 1479.69  5805.9 1480.24
#Mann= 3 ,-1 , 0
  4493.2     .05       0  4980.5     .05       0  5009.2     .05       0
Bank Sta=4980.5,5009.2
XS Rating Curve= 0 ,0
Exp/Cntr=0.3,0.1

Type RM Length L Ch R = 1 ,15500   ,500,500,500
BEGIN DESCRIPTION:
CHERRY SPRING CREEK 31.0
END DESCRIPTION:
XS GIS Cut Line= 3
      2731255.72     10162953.09      2731605.47     10162723.09
      2731655.68     10161853.14
#Sta/Elev= 30
  4581.4 1478.89  4617.3  1478.3    4631 1476.78  4676.3  1475.5  4790.7 1468.18
  4805.8 1467.98  4811.8  1466.9    4848 1464.62  4928.4 1460.99  4956.4 1460.77
  4971.5 1460.02  4992.6 1457.01  5015.7 1456.53  5016.2 1456.03  5044.4 1456.53
  5059.5 1457.71  5070.1 1459.77  5110.2  1463.7  5140.2 1465.74  5180.3 1465.39
  5220.3 1466.82  5270.4 1466.81  5308.3 1467.74  5350.6 1468.66  5390.6 1468.45
  5436.6 1470.15  5470.8 1469.64    5591 1472.04  5780.5 1477.49  5871.4 1478.61
#Mann= 5 ,-1 , 0
  4581.4     .05       0  5015.7     .03       0  5044.4     .05       0
  5059.5     .12       0  5308.3     .05       0
Bank Sta=5015.7,5044.4
XS Rating Curve= 0 ,0
Exp/Cntr=0.3,0.1

Type RM Length L Ch R = 1 ,15000   ,500,500,500
BEGIN DESCRIPTION:
CHERRY SPRING CREEK 30.0
END DESCRIPTION:
XS GIS Cut Line= 3
       2731455.7     10163003.11      2731940.09     10163063.19
      2732905.72      10162653.1
#Sta/Elev= 30
  4511.9 1472.96  4642.9 1466.59  4716.7 1465.93  4797.7 1462.99  4904.9 1454.46
  4959.5 1453.72  4971.1 1451.15  4971.6 1450.65  4999.9 1451.15  5017.7 1451.43
  5035.9 1458.08  5082.1 1461.79  5125.6 1460.07    5165 1461.38  5170.5 1462.85
  5188.7  1463.7  5194.1 1466.29  5212.4 1464.83  5217.8 1465.98  5223.4 1464.09
    5376 1465.88  5552.5 1471.22  5858.1 1484.66  5881.7  1487.1  5910.8 1488.03
  5918.7 1489.67    5929 1488.97    5973 1494.82  6005.4    1494  6049.1 1495.33
#Mann= 3 ,-1 , 0
  4511.9     .05       0  4971.1     .05       0  4999.9     .05       0
Bank Sta=4971.1,4999.9
XS Rating Curve= 0 ,0
Exp/Cntr=0.3,0.1

Type RM Length L Ch R = 1 ,14500   ,500,500,500
BEGIN DESCRIPTION:
CHERRY SPRING CREEK 29.0
END DESCRIPTION:
XS GIS Cut Line= 3
      2731305.72     10163103.13      2732005.75     10163508.83
      2732405.65     10163303.13
#Sta/Elev= 30
  4190.9 1476.07  4257.5 1474.26  4365.2 1468.52  4498.6 1464.22  4594.7 1463.57
  4653.2 1461.84  4659.2 1462.49  4739.6 1461.51    4863 1459.14  4872.8 1458.55
  4878.7 1457.15  4894.5 1456.31  4900.3 1456.92  4930.6 1454.72  4953.3 1451.07
  4959.1 1451.87  4974.8 1447.46  4980.6 1447.92  4984.8 1446.39  4985.3 1445.89
  5013.7 1446.39  5047.9 1450.24  5092.3 1449.06  5108.8 1451.51  5136.6 1452.53
  5153.2 1454.61    5181 1455.07  5219.7 1457.91  5308.4 1461.13  5449.7 1468.59
#Mann= 3 ,-1 , 0
  4190.9     .05       0  4984.8     .05       0  5013.7     .05       0
Bank Sta=4984.8,5013.7
XS Rating Curve= 0 ,0
Exp/Cntr=0.3,0.1

Type RM Length L Ch R = 1 ,14000   ,500,500,500
BEGIN DESCRIPTION:
CHERRY SPRING CREEK 28.0
END DESCRIPTION:
XS GIS Cut Line= 3
      2731455.66     10163853.11      2732167.32     10163973.07
       2732555.7     10163603.09
#Sta/Elev= 30
  4278.3 1470.74    4306 1471.11  4311.1 1469.65  4318.9 1470.09  4420.3 1462.67
  4521.7 1458.26  4608.6 1456.13  4815.8    1455  4850.6 1452.93  4866.5 1450.07
  4886.8 1450.99    4906 1449.38  4947.6 1448.71  4966.5 1445.24  4991.5 1443.74
    4992 1443.24  5020.4 1443.74  5055.3 1445.53  5090.8 1449.97    5105 1449.71
  5147.5 1453.26  5196.8 1454.24  5204.1 1455.56  5267.6 1459.49    5317 1460.84
  5331.1  1462.4  5359.4 1462.32  5479.9 1466.37    5501 1468.48  5536.4 1468.61
#Mann= 3 ,-1 , 0
  4278.3     .05       0  4991.5     .05       0  5020.4     .05       0
Bank Sta=4991.5,5020.4
XS Rating Curve= 0 ,0
Exp/Cntr=0.3,0.1

Type RM Length L Ch R = 1 ,13500   ,500,500,500
BEGIN DESCRIPTION:
CHERRY SPRING CREEK 27.0
END DESCRIPTION:
XS GIS Cut Line= 3
      2731339.17     10164156.89       2732291.3     10164444.09
       2732705.7     10164553.12
#Sta/Elev= 30
  4005.5 1460.75  4041.4 1461.66  4046.6    1461  4112.6 1461.58  4117.8 1460.81
  4178.5 1460.61  4359.1  1455.5  4496.3 1452.91  4808.8 1451.41  4836.5 1449.56
  4841.7 1450.67  4847.9 1449.06  4868.8 1446.56  4874.7 1444.82  4879.9 1445.43
  4900.1 1443.49    4921 1442.56  4945.9 1443.13  4999.7 1441.13  5012.8 1441.63
  5021.1 1440.47  5021.6 1439.97    5050 1440.47  5053.1 1444.33  5058.3 1444.02
  5076.9 1446.42  5107.9  1447.2  5289.9 1456.91  5330.2 1458.24  5428.5 1465.02
#Mann= 3 ,-1 , 0
  4005.5     .05       0  5021.1     .05       0    5050     .05       0
Bank Sta=5021.1,5050
XS Rating Curve= 0 ,0
Exp/Cntr=0.3,0.1

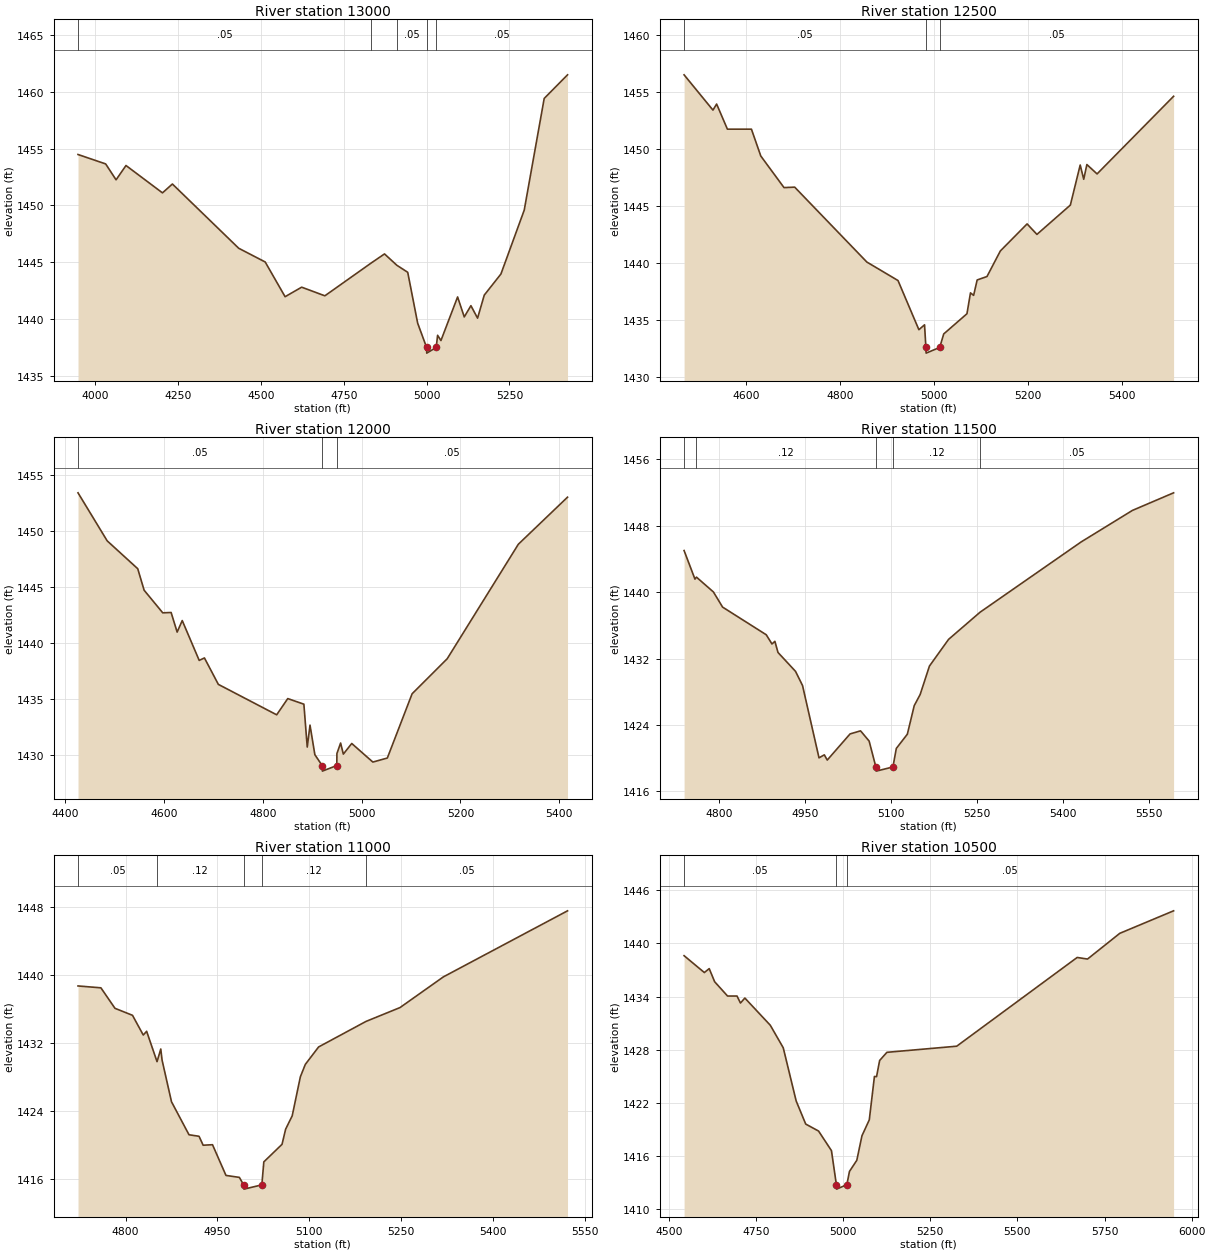
Type RM Length L Ch R = 1 ,13000   ,500,500,500
BEGIN DESCRIPTION:
CHERRY SPRING CREEK 26.0
END DESCRIPTION:
XS GIS Cut Line= 3
      2731130.91     10164941.62      2732182.76     10164899.28
      2732605.64     10164853.12
#Sta/Elev= 30
  3947.3 1454.49  4030.8 1453.66  4062.2 1452.26  4092.2 1453.52  4202.3 1451.11
  4232.3 1451.89  4432.5 1446.23  4512.5 1445.02  4572.6 1441.96  4622.6  1442.8
  4692.7 1442.04  4833.1 1444.94  4872.8 1445.73  4910.1 1444.73  4942.9 1444.11
  4972.9 1439.63  4999.9 1437.49  5000.4 1436.99  5028.9 1437.49  5033.1 1438.56
  5043.2  1438.1  5093.5 1441.94  5113.6 1440.18  5133.7 1441.17  5153.8 1440.07
    5174  1442.1  5224.3 1443.96  5294.7 1449.59    5355 1459.43  5425.4 1461.51
#Mann= 5 ,-1 , 0
  3947.3     .05       0  4833.1     .12       0  4910.1     .05       0
  4999.9     .05       0  5028.9     .05       0
Bank Sta=4999.9,5028.9
XS Rating Curve= 0 ,0
Exp/Cntr=0.3,0.1

Type RM Length L Ch R = 1 ,12500   ,500,500,500
BEGIN DESCRIPTION:
CHERRY SPRING CREEK 25.0
END DESCRIPTION:
XS GIS Cut Line= 3
      2731605.64     10165503.12      2732125.02     10165392.15
      2732505.71     10165053.09
#Sta/Elev= 30
  4468.9 1456.49  4530.3  1453.4  4538.1 1453.93    4561 1451.73  4612.1 1451.73
    4632 1449.38  4681.4 1446.61  4704.1 1446.65  4857.5 1440.09  4923.8 1438.47
  4968.2 1434.16  4980.2 1434.59  4983.1 1432.61  4983.6 1432.11  5012.5 1432.61
    5021 1433.79  5070.4 1435.56  5077.9 1437.39  5084.6 1437.17  5092.1 1438.52
    5113 1438.82  5141.4 1441.06  5198.3 1443.43  5219.2 1442.51  5290.3 1445.08
  5311.2 1448.59  5318.7 1447.34  5325.4 1448.63  5347.1 1447.81  5509.8 1454.61
#Mann= 3 ,-1 , 0
  4468.9     .05       0  4983.1     .05       0  5012.5     .05       0
Bank Sta=4983.1,5012.5
XS Rating Curve= 0 ,0
Exp/Cntr=0.3,0.1

Type RM Length L Ch R = 1 ,12000   ,500,500,500
BEGIN DESCRIPTION:
CHERRY SPRING CREEK 24.0
END DESCRIPTION:
XS GIS Cut Line= 3
       2732105.7     10166303.08      2732358.56     10165788.34
       2732605.7     10165453.09
#Sta/Elev= 30
  4426.5  1453.4  4485.5 1449.11  4547.3 1446.62  4560.2  1444.7  4597.9 1442.68
  4614.8 1442.71    4627 1440.96  4637.3 1441.99  4671.6 1438.43  4682.2 1438.65
  4710.3 1436.29  4828.3 1433.57  4850.7 1435.02  4883.3 1434.52  4890.1 1430.69
  4895.7 1432.65  4905.5 1430.01  4920.2 1429.04  4920.7 1428.54  4949.9 1429.04
  4950.1 1430.11  4957.6 1431.05  4963.1 1430.06  4980.1 1431.01  5022.8 1429.35
  5052.1 1429.71  5102.2 1435.45  5173.2 1438.58  5317.1 1448.81  5416.5 1453.01
#Mann= 3 ,-1 , 0
  4426.5     .05       0  4920.2     .05       0  4949.9     .05       0
Bank Sta=4920.2,4949.9
XS Rating Curve= 0 ,0
Exp/Cntr=0.3,0.1

Type RM Length L Ch R = 1 ,11500   ,500,500,500
BEGIN DESCRIPTION:
CHERRY SPRING CREEK 23.0
END DESCRIPTION:
XS GIS Cut Line= 3
      2732605.68     10166403.13      2732663.48     10166147.79
      2732830.68     10165578.12
#Sta/Elev= 30
  4738.2    1445  4757.2 1441.56  4759.8  1441.8  4789.5 1440.01  4805.5 1438.19
  4881.8 1434.86  4891.8 1433.75  4896.9 1434.07  4902.3 1432.73    4933 1430.45
  4945.2 1428.75    4974 1420.04  4983.3  1420.4  4988.4 1419.77  5028.3 1422.92
  5046.6 1423.29  5061.6 1422.06  5073.4 1418.94  5073.9 1418.44  5103.2 1418.94
  5109.1 1421.17  5128.4 1422.89  5140.4 1426.32  5150.8 1427.67    5167 1431.09
  5200.4  1434.3  5255.4 1437.57  5432.2 1446.04  5521.7 1449.83  5593.7 1451.95
#Mann= 5 ,-1 , 0
  4738.2     .05       0  4759.8     .12       0  5073.4     .07       0
  5103.2     .12       0  5255.4     .05       0
Bank Sta=5073.4,5103.2
XS Rating Curve= 0 ,0
Exp/Cntr=0.3,0.1

Type RM Length L Ch R = 1 ,11000   ,500,500,500
BEGIN DESCRIPTION:
CHERRY SPRING CREEK 22.0
END DESCRIPTION:
XS GIS Cut Line= 3
      2733255.69     10166403.13      2733140.79      10166150.2
       2732950.5     10165664.34
#Sta/Elev= 30
  4722.2 1438.69  4759.6 1438.47  4782.6 1436.06  4811.2 1435.24  4828.8 1432.92
  4834.3 1433.36  4851.3 1429.79  4857.4 1431.28  4859.5 1429.98  4874.9 1425.08
  4903.5  1421.2  4919.9 1421.02  4926.6 1419.97  4941.9 1420.03  4963.9 1416.42
  4985.8 1416.19  4992.7 1415.31  4993.2 1414.81  5022.5 1415.31  5025.7 1418.01
  5055.5 1420.08  5061.3 1421.85  5072.1 1423.43  5085.4 1428.01  5093.5 1429.47
  5115.2 1431.52  5192.6 1434.52  5248.2 1436.15  5319.1 1439.76  5521.8 1447.52
#Mann= 5 ,-1 , 0
  4722.2     .05       0  4851.3     .12       0  4992.7     .07       0
  5022.5     .12       0  5192.6     .05       0
Bank Sta=4992.7,5022.5
XS Rating Curve= 0 ,0
Exp/Cntr=0.3,0.1

Type RM Length L Ch R = 1 ,10500   ,500,500,500
BEGIN DESCRIPTION:
CHERRY SPRING CREEK 21.0
END DESCRIPTION:
XS GIS Cut Line= 3
      2733855.68     10166453.11       2733622.8     10166060.94
      2733082.26     10165281.91
#Sta/Elev= 30
  4543.9 1438.62    4602 1436.72    4616 1437.16  4631.6 1435.68  4668.6 1434.07
  4695.8 1434.07  4705.6 1433.28  4718.3 1433.84  4791.3 1430.77  4828.4 1428.23
  4865.4 1422.24  4892.8 1419.63  4929.7 1418.84  4966.7 1416.63  4980.8 1412.79
  4981.3 1412.29  5010.8 1412.79  5018.4 1414.29  5039.4 1415.54  5054.2 1418.31
  5075.2  1420.1    5090    1425  5096.1 1424.98  5104.9  1426.8  5125.8 1427.72
    5326 1428.41  5671.6 1438.42  5701.3 1438.24  5793.8 1441.14  5948.2 1443.68
#Mann= 3 ,-1 , 0
  4543.9     .05       0  4980.8     .05       0  5010.8     .05       0
Bank Sta=4980.8,5010.8
XS Rating Curve= 0 ,0
Exp/Cntr=0.3,0.1

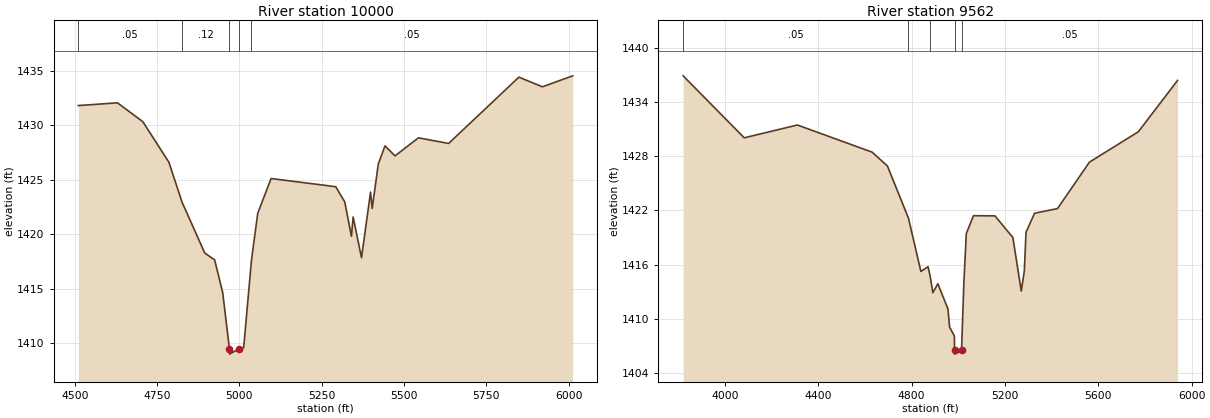
Type RM Length L Ch R = 1 ,10000   ,438,438,438
BEGIN DESCRIPTION:
CHERRY SPRING CREEK 20.0
END DESCRIPTION:
XS GIS Cut Line= 3
      2734200.31     10166254.13      2734023.59     10165797.75
      2733839.19     10164802.69
#Sta/Elev= 30
  4510.6 1431.81  4629.7 1432.06  4706.7 1430.33  4785.8 1426.61  4826.2 1422.91
  4894.8 1418.27  4924.8 1417.64  4949.3 1414.63  4969.6 1409.49  4970.1 1408.99
  4999.6 1409.49  5012.9 1409.57  5036.6 1417.61  5055.6 1421.92  5096.2 1425.11
  5292.5 1424.36    5320 1422.96  5340.2 1419.81  5345.3 1421.58  5370.8 1417.84
  5398.2 1423.86  5403.3 1422.37  5421.7 1426.43    5442 1428.11  5472.5 1427.19
  5543.7 1428.85  5635.3 1428.33  5848.8 1434.42    5920 1433.53    6012 1434.54
#Mann= 5 ,-1 , 0
  4510.6     .05       0  4826.2     .12       0  4969.6     .07       0
  4999.6     .12       0  5036.6     .05       0
Bank Sta=4969.6,4999.6
XS Rating Curve= 0 ,0
Exp/Cntr=0.3,0.1

Type RM Length L Ch R = 1 ,9562    ,562,562,562
BEGIN DESCRIPTION:
CHERRY SPRING CREEK 19.0
END DESCRIPTION:
XS GIS Cut Line= 3
      2734144.74     10166747.21       2734400.5       10165597.
      2734200.54     10164678.82
#Sta/Elev= 30
  3821.7 1436.92  4083.3 1430.05  4311.1 1431.47  4631.2 1428.46  4696.7 1426.93
    4787 1421.14  4840.1 1415.24  4870.8 1415.77  4880.4 1414.65  4891.3 1412.89
  4912.8 1413.88  4956.3 1411.08    4963 1409.08  4983.5 1408.09  4984.4 1406.58
  4984.9 1406.08  5014.4 1406.58  5024.4 1414.09  5034.7 1419.44  5065.4 1421.42
  5157.5  1421.4  5234.2    1419  5270.1 1413.07  5283.3 1415.31  5290.5 1419.59
  5327.2 1421.69  5425.4 1422.21  5562.4 1427.36  5771.6 1430.72  5939.7 1436.41
#Mann= 5 ,-1 , 0
  3821.7     .05       0    4787     .12       0  4880.4     .05       0
  4984.4     .05       0  5014.4     .05       0
Bank Sta=4984.4,5014.4
XS Rating Curve= 0 ,0
Exp/Cntr=0.3,0.1