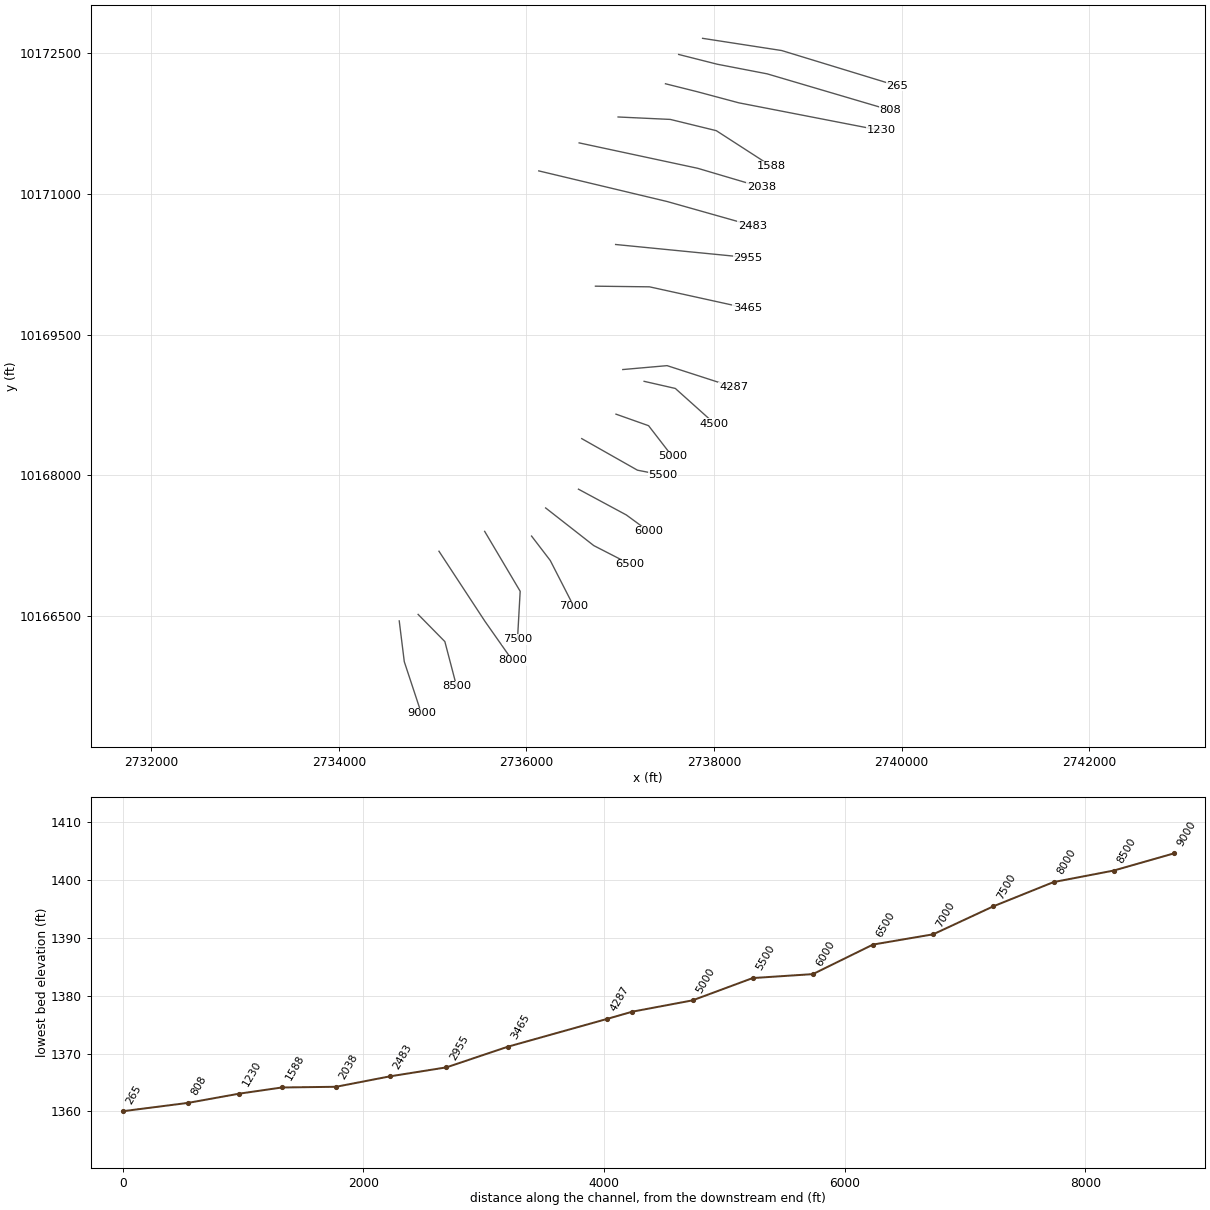
HEC-RAS study CHERRY SPRING CREEK.prj: CHERRY SPRING CREEK Base Level Engineering

--- CHERRY SPRING CREEK.g01 (geometry) --- (continued)

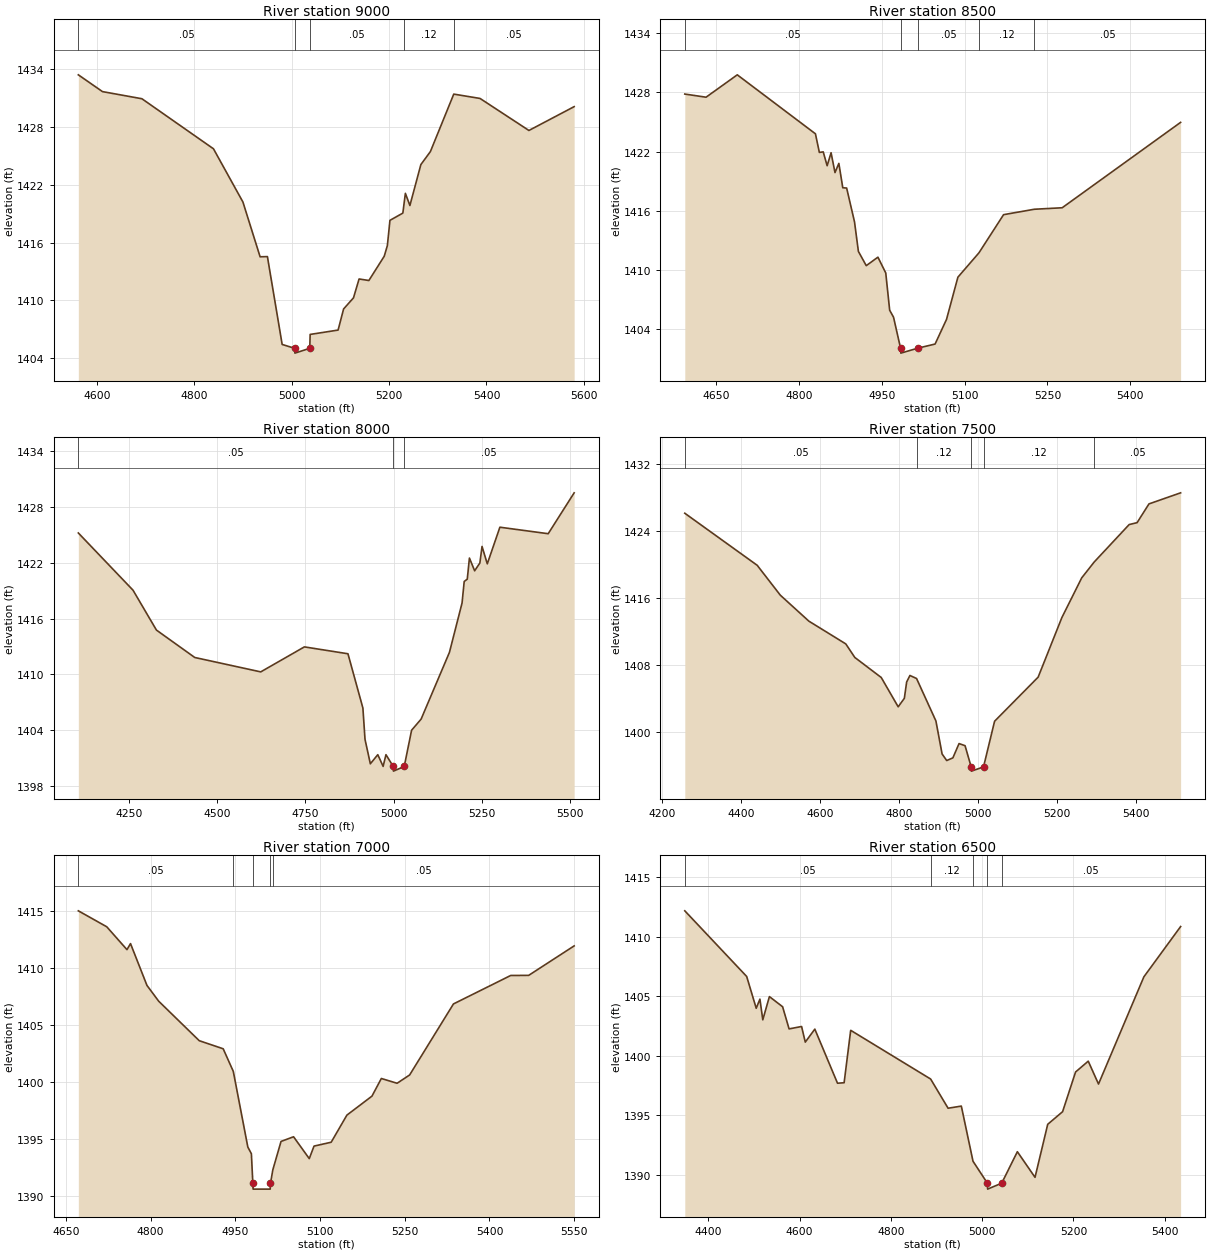
Type RM Length L Ch R = 1 ,9000    ,500,500,500
BEGIN DESCRIPTION:
CHERRY SPRING CREEK 18.0
END DESCRIPTION:
XS GIS Cut Line= 3
      2734644.74      10166448.6      2734698.66     10166013.53
      2734880.76     10165462.75
#Sta/Elev= 30
  4561.6 1433.39  4611.2 1431.65  4692.2 1430.91  4839.2 1425.72  4899.7  1420.2
    4935 1414.52    4950 1414.54  4980.3 1405.43    5006 1405.03  5006.5 1404.53
    5037 1405.03  5037.8 1406.47  5095.2 1406.92  5106.5 1409.11  5126.8 1410.26
  5138.3 1412.22  5158.4 1412.06    5190 1414.58  5196.4 1415.68  5201.7  1418.3
  5228.2 1419.05  5230.7 1420.04  5233.4  1421.1  5242.7 1419.84  5265.2 1424.08
  5284.8 1425.43  5332.8 1431.39  5386.8 1430.94  5487.2 1427.62  5580.1 1430.09
#Mann= 5 ,-1 , 0
  4561.6     .05       0    5006     .05       0    5037     .05       0
  5230.7     .12       0  5332.8     .05       0
Bank Sta=5006,5037
XS Rating Curve= 0 ,0
Exp/Cntr=0.3,0.1

Type RM Length L Ch R = 1 ,8500    ,500,500,500
BEGIN DESCRIPTION:
CHERRY SPRING CREEK 17.0
END DESCRIPTION:
XS GIS Cut Line= 3
      2734846.15       10166518.      2735131.19     10166228.18
      2735255.68     10165753.12
#Sta/Elev= 30
  4593.5 1427.84    4632 1427.52  4688.5 1429.79    4830 1423.81  4837.1 1421.92
  4844.1 1421.98  4851.2 1420.57  4858.3 1421.89  4865.4 1419.88  4872.4 1420.81
  4879.5 1418.34  4886.5 1418.31  4900.7 1414.89  4907.8 1411.88    4922 1410.44
  4943.1  1411.3  4957.3  1409.7  4964.4 1405.92  4971.4 1405.21  4984.1 1402.07
  4984.6 1401.57  5015.2 1402.07  5046.6 1402.49  5067.3 1404.99  5087.9 1409.27
    5126 1411.74  5170.6 1415.61  5226.4 1416.16  5276.7 1416.31  5491.1 1424.97
#Mann= 5 ,-1 , 0
  4593.5     .05       0  4984.1     .05       0  5015.2     .05       0
    5126     .12       0  5226.4     .05       0
Bank Sta=4984.1,5015.2
XS Rating Curve= 0 ,0
Exp/Cntr=0.3,0.1

Type RM Length L Ch R = 1 ,8000    ,500,500,500
BEGIN DESCRIPTION:
CHERRY SPRING CREEK 16.0
END DESCRIPTION:
XS GIS Cut Line= 3
      2735068.37      10167191.6      2735558.27     10166444.74
      2735851.95     10166026.56
#Sta/Elev= 30
  4106.8 1425.21  4261.7 1419.05    4328 1414.76  4436.5 1411.81  4623.4 1410.26
    4747 1412.95  4870.4 1412.21  4912.7 1406.37  4918.7    1403  4933.8 1400.37
  4954.9 1401.35    4970 1400.09    4978 1401.35  4998.7 1400.08  4999.2 1399.58
  5029.8 1400.08  5050.6 1403.98  5077.6 1405.18  5157.8 1412.36  5193.5 1417.67
  5199.6 1419.99  5208.3 1420.24  5214.4 1422.51  5229.2 1421.14    5244 1421.98
  5250.1 1423.76    5265 1421.89  5300.7 1425.83  5437.5 1425.13    5511 1429.53
#Mann= 3 ,-1 , 0
  4106.8     .05       0  4998.7     .05       0  5029.8     .05       0
Bank Sta=4998.7,5029.8
XS Rating Curve= 0 ,0
Exp/Cntr=0.3,0.1

Type RM Length L Ch R = 1 ,7500    ,500,500,500
BEGIN DESCRIPTION:
CHERRY SPRING CREEK 15.0
END DESCRIPTION:
XS GIS Cut Line= 3
       2735555.7     10167403.09      2735934.23     10166764.56
      2735905.69     10166253.16
#Sta/Elev= 30
  4257.7 1426.11  4440.9 1419.91  4499.4 1416.35  4571.6 1413.26    4665 1410.55
  4687.8 1408.94  4754.7 1406.55  4797.6 1403.06  4813.2 1404.07    4819 1406.01
  4827.3 1406.79  4844.1 1406.43  4893.1 1401.37  4908.7 1397.44  4920.4 1396.66
    4936 1396.98  4951.6 1398.68  4966.8 1398.43  4982.3  1395.9  4982.8  1395.4
  5013.5  1395.9  5041.5 1401.34  5151.7 1406.59  5211.8 1413.69  5261.9 1418.41
  5293.5  1420.3    5382 1424.76  5402.1 1424.99  5432.1 1427.22  5512.2 1428.54
#Mann= 5 ,-1 , 0
  4257.7     .05       0  4844.1     .12       0  4982.3     .07       0
  5013.5     .12       0  5293.5     .05       0
Bank Sta=4982.3,5013.5
XS Rating Curve= 0 ,0
Exp/Cntr=0.3,0.1

Type RM Length L Ch R = 1 ,7000    ,500,500,500
BEGIN DESCRIPTION:
CHERRY SPRING CREEK 14.0
END DESCRIPTION:
XS GIS Cut Line= 3
      2736055.71     10167353.08       2736255.1     10167092.64
      2736505.67     10166603.14
#Sta/Elev= 30
    4672 1415.02  4722.3 1413.62  4758.1 1411.61  4764.4 1412.14  4793.5 1408.47
  4814.3 1407.08  4886.1 1403.61  4928.5  1402.9  4946.4 1400.91  4972.1 1394.27
  4978.4 1393.68    4981 1391.07  4981.5 1390.57  5011.7 1390.57  5012.2 1391.07
  5016.4 1392.27  5030.9 1394.76  5053.1 1395.17  5080.9 1393.25  5089.3 1394.35
  5119.7 1394.69  5147.5 1397.07  5191.9 1398.74  5208.5 1400.29  5236.4 1399.87
  5258.6  1400.6  5336.2 1406.84  5437.6 1409.34  5469.4 1409.35  5549.9 1411.94
#Mann= 5 ,-1 , 0
    4672     .05       0  4946.4     .12       0    4981     .07       0
  5012.2     .12       0  5016.4     .05       0
Bank Sta=4981,5012.2
XS Rating Curve= 0 ,0
Exp/Cntr=0.3,0.1

Type RM Length L Ch R = 1 ,6500    ,500,500,500
BEGIN DESCRIPTION:
CHERRY SPRING CREEK 13.0
END DESCRIPTION:
XS GIS Cut Line= 3
      2736205.68     10167653.12      2736718.83      10167251.7
      2737105.73     10167053.09
#Sta/Elev= 30
  4348.5 1412.16  4484.1 1406.65    4505 1403.98  4513.1 1404.75  4519.4 1403.01
  4533.9 1404.96  4562.8 1404.11    4577 1402.25  4604.4 1402.45  4612.5 1401.14
  4633.4 1402.23  4683.1 1397.69  4697.6 1397.73    4712 1402.13  4887.2 1398.04
  4925.4 1395.59  4954.4 1395.77    4980 1391.14  5011.5  1389.3    5012  1388.8
  5042.9  1389.3  5077.2 1391.94  5115.9 1389.79  5143.7 1394.24  5176.3  1395.3
  5204.7 1398.63  5232.5 1399.54    5255 1397.62  5354.4 1406.62  5434.9 1410.84
#Mann= 5 ,-1 , 0
  4348.5     .05       0  4887.2     .12       0    4980     .05       0
  5011.5     .05       0  5042.9     .05       0
Bank Sta=5011.5,5042.9
XS Rating Curve= 0 ,0
Exp/Cntr=0.3,0.1

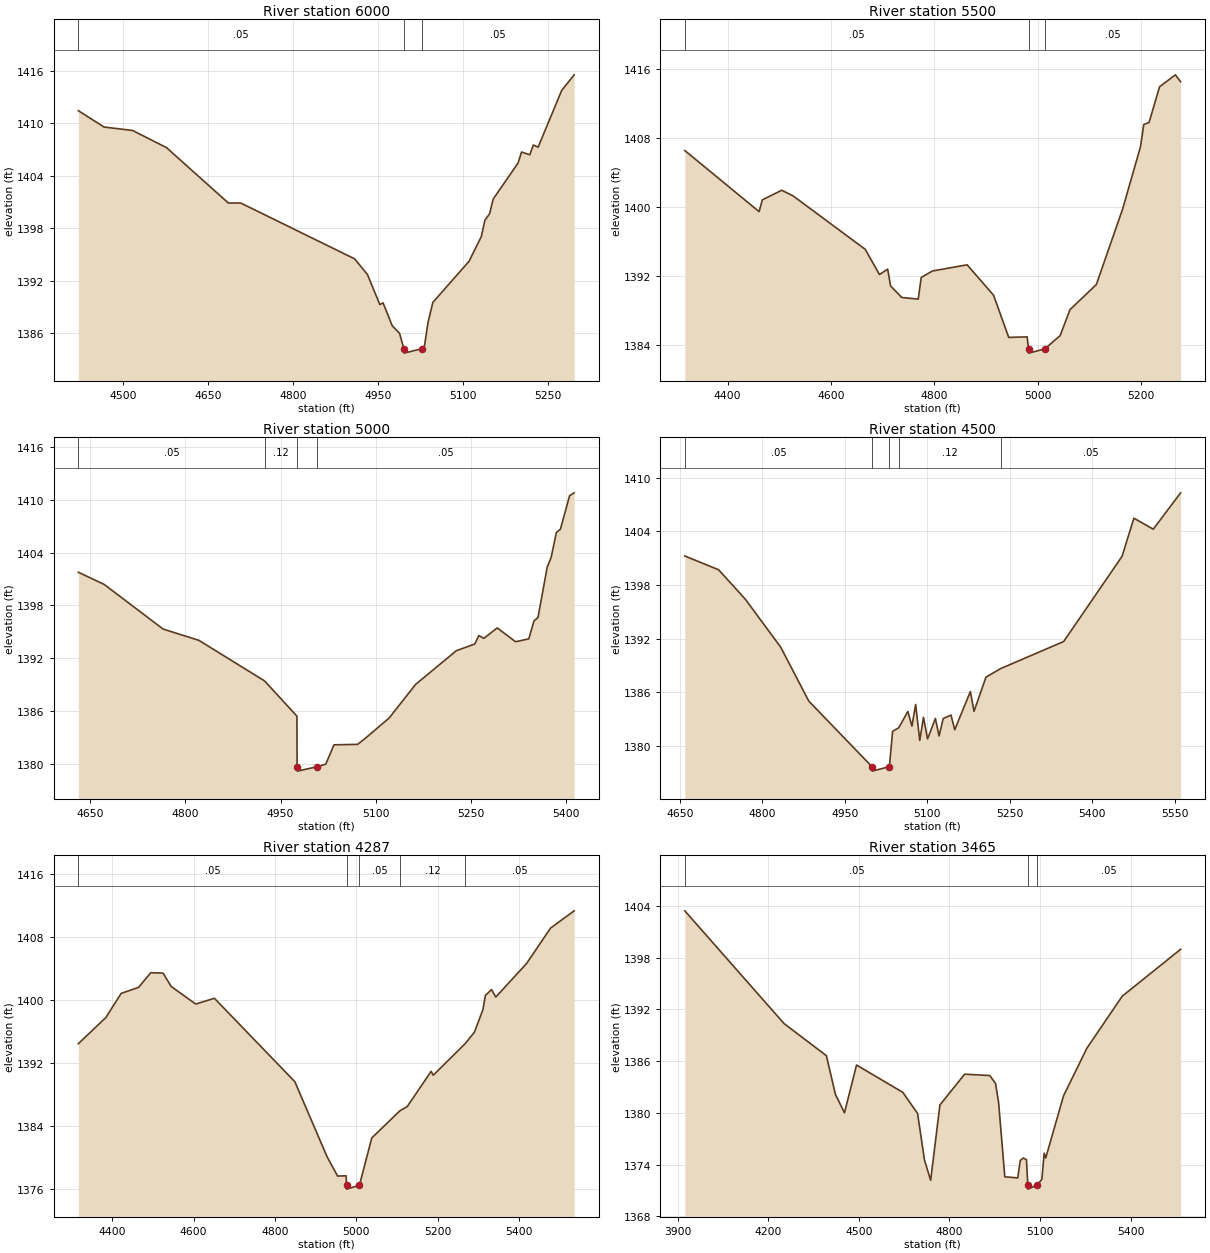
Type RM Length L Ch R = 1 ,6000    ,500,500,500
BEGIN DESCRIPTION:
CHERRY SPRING CREEK 12.0
END DESCRIPTION:
XS GIS Cut Line= 3
      2736555.66     10167853.12      2737065.98     10167578.34
      2737305.67     10167403.12
#Sta/Elev= 30
  4420.4 1411.42  4465.9 1409.55  4516.2 1409.16  4576.2  1407.2  4685.7 1400.86
  4707.6 1400.86  4908.8 1394.48  4931.5 1392.69  4953.4 1389.25  4959.1 1389.45
  4975.3 1386.83  4988.3 1385.96  4995.8  1384.2  4996.3  1383.7  5027.4  1384.2
  5032.4 1384.56  5038.6 1387.21  5047.1  1389.5  5111.1  1394.2  5132.8 1397.03
    5139 1398.87  5147.5 1399.65  5153.7 1401.31  5197.7 1405.43  5203.9 1406.69
  5218.5 1406.38  5224.7  1407.5  5233.2 1407.25  5274.9 1413.74  5296.9 1415.52
#Mann= 3 ,-1 , 0
  4420.4     .05       0  4995.8     .05       0  5027.4     .05       0
Bank Sta=4995.8,5027.4
XS Rating Curve= 0 ,0
Exp/Cntr=0.3,0.1

Type RM Length L Ch R = 1 ,5500    ,500,500,500
BEGIN DESCRIPTION:
CHERRY SPRING CREEK 11.0
END DESCRIPTION:
XS GIS Cut Line= 3
      2736590.66     10168392.21      2737184.73      10168055.6
      2737455.69     10168003.11
#Sta/Elev= 30
  4317.2 1406.58  4460.9 1399.47  4467.1 1400.84  4504.6 1401.96  4526.2 1401.32
  4666.2 1395.09  4693.6 1392.16  4709.5 1392.79  4715.2 1390.83  4736.8 1389.49
  4768.6  1389.3  4774.4 1391.82    4796 1392.57  4863.2 1393.29  4914.3 1389.75
  4943.6 1384.85  4979.2 1384.91  4981.9 1383.52  4982.4 1383.02  5013.5 1383.52
  5043.1 1385.06  5062.1 1388.08    5113 1390.99    5164  1399.8  5198.4 1407.02
  5204.7 1409.61  5214.9 1409.83  5235.3 1413.99  5265.8 1415.38    5276 1414.58
#Mann= 3 ,-1 , 0
  4317.2     .05       0  4981.9     .05       0  5013.5     .05       0
Bank Sta=4981.9,5013.5
XS Rating Curve= 0 ,0
Exp/Cntr=0.3,0.1

Type RM Length L Ch R = 1 ,5000    ,500,500,500
BEGIN DESCRIPTION:
CHERRY SPRING CREEK 10.0
END DESCRIPTION:
XS GIS Cut Line= 3
      2736955.69     10168653.11      2737303.32     10168529.96
      2737555.66     10168203.14
#Sta/Elev= 30
  4631.2 1401.77  4672.2 1400.37  4764.9 1395.31  4821.3 1394.03  4924.8 1389.42
  4975.8 1385.42  4976.1 1379.67  4976.6 1379.17  5007.7 1379.67  5021.3 1379.96
  5034.3 1382.16  5071.5 1382.21  5084.5 1382.95  5121.3 1385.21  5162.9 1389.02
  5227.3 1392.86  5256.2 1393.61  5262.6 1394.57  5270.7 1394.26  5291.6 1395.44
  5320.6 1393.87  5341.4  1394.2  5349.6 1396.24  5355.9 1396.62  5370.4 1402.34
  5376.7 1403.47  5384.9 1406.29  5391.2 1406.65  5405.7 1410.46  5412.9 1410.79
#Mann= 4 ,-1 , 0
  4631.2     .05       0  4924.8     .12       0  4976.1     .05       0
  5007.7     .05       0
Bank Sta=4976.1,5007.7
XS Rating Curve= 0 ,0
Exp/Cntr=0.3,0.1

Type RM Length L Ch R = 1 ,4500    ,213,213,213
BEGIN DESCRIPTION:
CHERRY SPRING CREEK 9.0
END DESCRIPTION:
XS GIS Cut Line= 3
      2737255.71     10169003.11      2737588.36     10168927.22
      2738005.71     10168553.08
#Sta/Elev= 30
  4658.8 1401.24  4720.3  1399.7  4768.8 1396.42  4833.1 1391.07  4884.4 1385.03
  4999.2 1377.72  4999.7 1377.22  5030.9 1377.72  5036.7 1381.66  5047.9 1382.06
  5064.4 1383.88  5071.9 1382.25  5078.6 1384.66  5086.1 1380.65  5092.8 1383.23
  5100.3 1380.82  5114.5  1383.1  5121.3 1381.14  5128.7 1383.09  5142.9 1383.48
  5149.7 1381.84  5178.1  1386.1  5184.8  1383.9  5206.5 1387.71  5233.3 1388.67
  5347.8 1391.69  5453.9 1401.19  5475.6 1405.46  5510.7 1404.23  5560.5 1408.29
#Mann= 5 ,-1 , 0
  4658.8     .05       0  4999.2     .05       0  5030.9     .05       0
  5047.9     .12       0  5233.3     .05       0
Bank Sta=4999.2,5030.9
XS Rating Curve= 0 ,0
Exp/Cntr=0.3,0.1

Type RM Length L Ch R = 1 ,4287    ,822,822,822
BEGIN DESCRIPTION:
Mapping XS 681503b0
END DESCRIPTION:
XS GIS Cut Line= 3
      2737028.27     10169128.66      2737500.54     10169170.33
      2738208.89     10168941.16
#Sta/Elev= 30
  4316.6 1394.42  4384.3 1397.75  4421.8 1400.81  4464.6 1401.58  4494.7 1403.44
  4524.8 1403.39  4544.9 1401.69  4605.1 1399.46    4651 1400.19  4848.7  1389.6
  4927.7 1380.09  4953.8 1377.61  4974.8 1377.64  4975.8 1376.45  4976.3 1375.95
  5007.5 1376.45  5037.8 1382.45  5106.7 1385.89    5125 1386.44  5183.7 1390.91
    5189 1390.42  5268.1 1394.47  5290.3 1395.91  5311.1 1398.78    5317 1400.55
  5332.1  1401.3  5342.6 1400.35  5418.3 1404.61  5477.1  1409.1  5535.2  1411.3
#Mann= 5 ,-1 , 0
  4316.6     .05       0  4975.8     .05       0  5007.5     .05       0
  5106.7     .12       0  5268.1     .05       0
Bank Sta=4975.8,5007.5
XS Rating Curve= 0 ,0
Exp/Cntr=0.3,0.1

Type RM Length L Ch R = 1 ,3465    ,510,510,510
BEGIN DESCRIPTION:
Mapping XS 5d9f3f49
END DESCRIPTION:
XS GIS Cut Line= 3
      2736736.63     10170017.55      2737313.04     10170010.61
      2738354.67     10169781.45
#Sta/Elev= 30
    3923 1403.44  4252.1 1390.36  4392.1 1386.65  4422.1 1382.16  4452.1 1380.02
  4492.1 1385.56  4645.5 1382.39  4694.4 1379.94  4717.2 1374.55  4737.7 1372.19
  4768.4 1380.93  4850.3  1384.5  4933.6 1384.34  4952.7 1383.43  4962.9 1381.21
  4983.4  1372.6  5026.3 1372.47  5034.6 1374.49  5044.8 1374.78  5055.1 1374.58
  5059.7 1371.67  5060.2 1371.17  5091.4 1371.67  5106.3 1372.32  5113.8 1375.33
  5118.9 1374.77  5177.9 1381.98  5255.2  1387.5  5372.5 1393.54    5566 1398.98
#Mann= 3 ,-1 , 0
    3923     .05       0  5059.7     .05       0  5091.4     .05       0
Bank Sta=5059.7,5091.4
XS Rating Curve= 0 ,0
Exp/Cntr=0.3,0.1

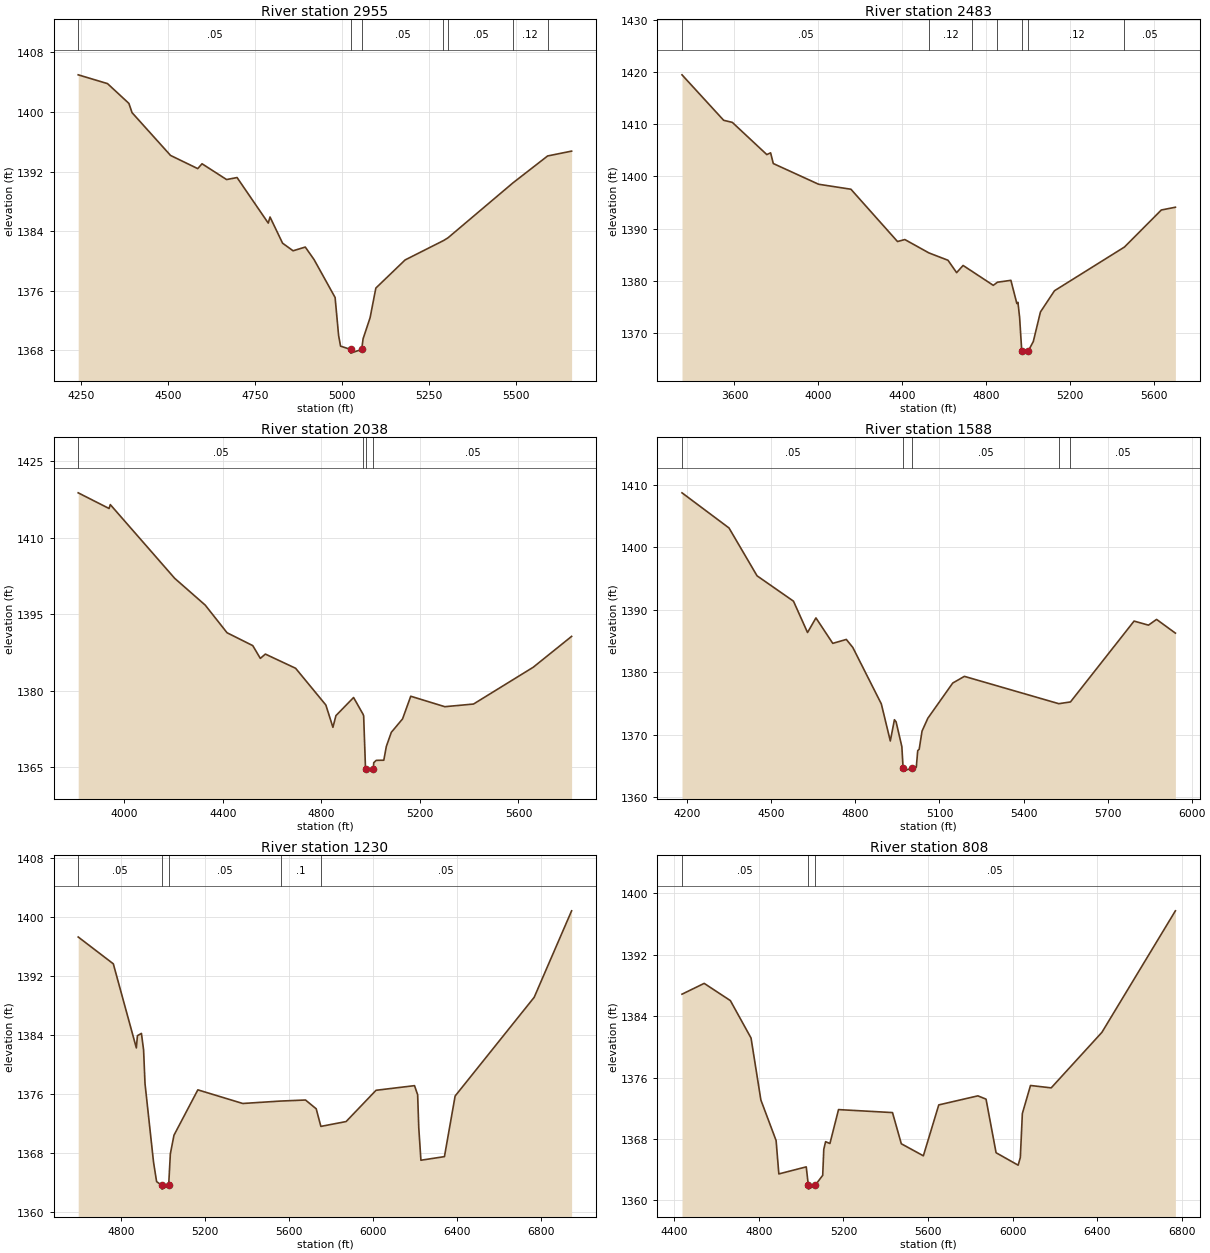
Type RM Length L Ch R = 1 ,2955    ,472,472,472
BEGIN DESCRIPTION:
Mapping XS 37d34fdd
END DESCRIPTION:
XS GIS Cut Line= 2
      2736951.97     10170461.99      2738361.15     10170323.16
#Sta/Elev= 30
    4243    1405  4327.1 1403.82  4388.5 1401.16  4397.5 1399.92    4508 1394.17
    4586  1392.4  4598.4 1393.05  4668.8 1390.93  4698.9  1391.2  4788.4 1385.08
  4793.5  1385.9  4829.5 1382.38  4859.7 1381.36  4894.7 1381.86    4920 1380.17
  4980.3 1375.08  4990.3 1369.98  4995.9 1368.55  5024.5 1368.11    5025 1367.61
  5056.6 1368.11  5060.6 1369.54  5080.7 1372.37  5097.2 1376.35  5181.2 1380.13
  5291.3 1382.73  5304.2  1383.1  5490.6 1390.48  5590.2  1394.1    5659 1394.75
#Mann= 7 ,-1 , 0
    4243     .05       0  5024.5     .05       0  5056.6     .05       0
  5291.3     .12       0  5304.2     .05       0  5490.6     .12       0
  5590.2     .05       0
Bank Sta=5024.5,5056.6
XS Rating Curve= 0 ,0
Exp/Cntr=0.3,0.1

Type RM Length L Ch R = 1 ,2483    ,445,445,445
BEGIN DESCRIPTION:
Mapping XS 7bfacb69
END DESCRIPTION:
XS GIS Cut Line= 3
      2736132.46     10171246.72      2737500.54     10170920.33
      2738410.28     10170663.38
#Sta/Elev= 30
  3349.8 1419.54  3548.4  1410.8  3589.6  1410.4  3754.1 1404.21  3772.1 1404.55
  3784.9 1402.49  4000.8 1398.51    4155 1397.55    4377  1387.5    4412 1387.88
  4526.8 1385.31  4617.6  1383.9  4658.8 1381.52  4689.6  1382.9    4732 1381.78
  4833.6 1379.08  4853.4 1379.68  4917.5 1380.04  4945.9 1375.58  4951.1 1375.81
  4959.1 1372.88  4969.1 1366.55  4969.6 1366.05  5001.2 1366.55  5024.3 1368.28
  5058.3 1373.96  5125.3 1378.04  5458.8 1386.44  5634.5 1393.56  5701.6 1394.09
#Mann= 7 ,-1 , 0
  3349.8     .05       0  4526.8     .12       0    4732     .05       0
  4853.4     .12       0  4969.1     .07       0  5001.2     .12       0
  5458.8     .05       0
Bank Sta=4969.1,5001.2
XS Rating Curve= 0 ,0
Exp/Cntr=0.3,0.1

Type RM Length L Ch R = 1 ,2038    ,450,450,450
BEGIN DESCRIPTION:
Mapping XS f1b8dadc
END DESCRIPTION:
XS GIS Cut Line= 3
        2736563.     10171545.34      2737826.92      10171274.5
      2738507.44     10171073.12
#Sta/Elev= 30
  3813.4 1418.81  3938.6 1415.74  3943.7  1416.5  4204.8 1402.06  4328.9  1396.8
  4417.5 1391.38  4521.8 1388.86  4552.5 1386.36  4572.9  1387.2  4695.7 1384.42
  4818.4 1377.22  4847.1 1372.85  4859.3 1375.14  4930.9 1378.69  4969.7 1375.38
  4971.8 1375.08  4979.3 1364.76  4979.8 1364.26  5011.4 1364.76  5012.7 1365.91
  5022.9 1366.37  5053.6  1366.4  5063.8  1369.1    5084 1371.86  5129.7  1374.5
  5162.9 1378.94  5301.2 1376.89  5417.6 1377.41  5659.9 1384.62  5815.7 1390.67
#Mann= 4 ,-1 , 0
  3813.4     .05       0  4969.7     .12       0  4979.3     .07       0
  5011.4     .05       0
Bank Sta=4979.3,5011.4
XS Rating Curve= 0 ,0
Exp/Cntr=0.3,0.1

Type RM Length L Ch R = 1 ,1588    ,358,358,358
BEGIN DESCRIPTION:
Mapping XS 8d77a524
END DESCRIPTION:
XS GIS Cut Line= 4
      2736978.21     10171821.56      2737535.46     10171795.52
      2738025.04     10171675.72      2738612.11     10171296.47
#Sta/Elev= 30
  4181.2 1408.75  4348.9 1403.12    4449 1395.45  4579.1 1391.38  4629.2 1386.36
  4659.2  1388.7  4719.3 1384.62  4767.6 1385.25  4790.8 1383.96  4892.5 1374.92
  4924.6 1368.97  4939.3 1372.38  4945.2 1372.04  4965.8 1368.07  4970.2 1364.64
  4970.8 1364.14  5002.5 1364.64  5017.3 1364.77  5022.5 1367.43  5027.7 1367.65
  5037.8 1370.55  5058.4 1372.61  5147.4 1378.26    5189 1379.33  5525.9 1374.95
  5567.5 1375.23  5794.5 1388.19  5845.9 1387.54  5874.8 1388.46    5942 1386.26
#Mann= 5 ,-1 , 0
  4181.2     .05       0  4970.2     .05       0  5002.5     .05       0
  5525.9     .12       0  5567.5     .05       0
Bank Sta=4970.2,5002.5
XS Rating Curve= 0 ,0
Exp/Cntr=0.3,0.1

Type RM Length L Ch R = 1 ,1230    ,422,422,422
BEGIN DESCRIPTION:
Mapping XS 48790529
END DESCRIPTION:
XS GIS Cut Line= 4
      2737483.41     10172175.72      2737816.71     10172092.39
      2738264.63      10171972.6      2739780.67     10171678.11
#Sta/Elev= 30
  4595.2 1397.27  4762.5 1393.63  4872.3 1382.22  4877.5 1383.88  4896.5 1384.19
  4906.8 1381.95  4913.6 1377.37  4954.3  1366.7  4968.8 1364.08    4994 1363.56
  4994.6 1363.06  5026.3 1363.56  5034.4 1367.85  5051.6 1370.37  5165.4 1376.53
  5379.4 1374.68  5560.5 1375.01  5678.5 1375.15  5729.5 1373.96  5751.8 1371.57
  5872.1 1372.23  6014.7 1376.47  6198.1  1377.1    6213 1375.87  6218.4 1371.37
  6228.6 1366.98  6340.7 1367.47  6391.6 1375.69  6768.5 1389.09  6946.8 1400.82
#Mann= 5 ,-1 , 0
  4595.2     .05       0    4994     .03       0  5026.3     .05       0
  5560.5      .1       0  5751.8     .05       0
Bank Sta=4994,5026.3
XS Rating Curve= 0 ,0
Exp/Cntr=0.3,0.1

Type RM Length L Ch R = 1 ,808     ,543,543,543
BEGIN DESCRIPTION:
Mapping XS 46526374
END DESCRIPTION:
XS GIS Cut Line= 4
      2737623.97     10172488.23      2738035.46     10172384.06
        2738568.     10172281.35      2739879.19     10171894.48
#Sta/Elev= 30
  4436.6 1386.87  4541.5 1388.28  4665.3 1386.04  4763.2 1381.16  4809.7 1373.09
  4881.7 1367.81  4894.7 1363.46  5024.3 1364.38  5034.2 1361.98  5034.7 1361.48
  5066.5 1361.98  5102.2 1363.28  5107.3 1366.67  5115.9 1367.66  5136.3 1367.42
    5177 1371.84  5432.3 1371.45    5474 1367.39  5578.3 1365.82  5651.2 1372.45
  5836.3 1373.63  5874.8  1373.2  5922.3 1366.22  6026.6  1364.6    6037  1365.6
  6046.6 1371.33  6085.1 1374.98    6183 1374.67  6422.8  1381.9  6770.5 1397.73
#Mann= 3 ,-1 , 0
  4436.6     .05       0  5034.2     .05       0  5066.5     .05       0
Bank Sta=5034.2,5066.5
XS Rating Curve= 0 ,0
Exp/Cntr=0.3,0.1

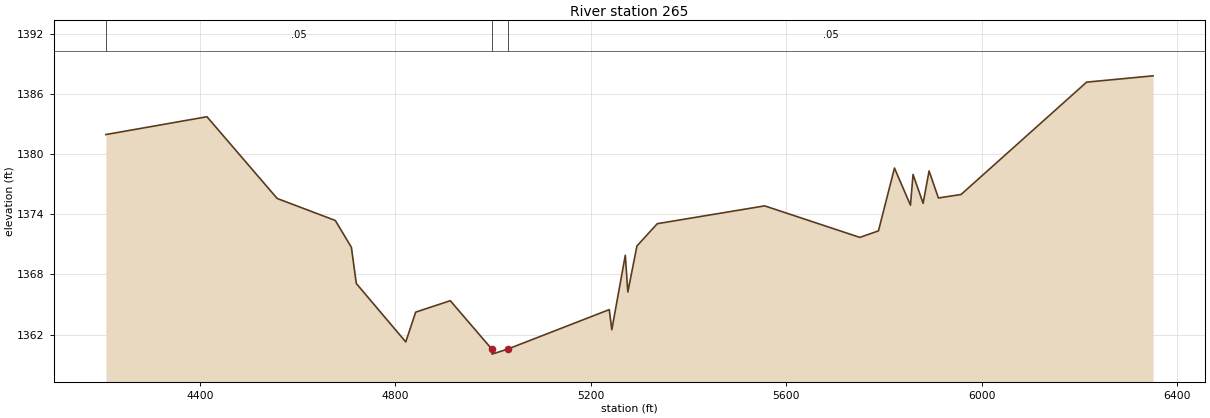
Type RM Length L Ch R = 1 ,265     ,0,0,0
BEGIN DESCRIPTION:
CHERRY SPRING CREEK 7.0
END DESCRIPTION:
XS GIS Cut Line= 3
      2737879.25     10172660.09      2738722.96     10172529.89
      2739955.67     10172153.12
#Sta/Elev= 30
  4207.8 1381.99  4414.6 1383.77  4558.3  1375.6  4677.2  1373.4  4710.1 1370.72
  4720.2  1367.1  4821.4 1361.26  4841.7 1364.24  4912.5 1365.38  4997.5 1360.54
    4998 1360.04  5029.8 1360.54  5237.8 1364.49    5243 1362.48  5270.6 1369.92
  5275.8 1366.25  5294.4 1370.85  5336.1 1373.08  5555.8 1374.86  5750.5 1371.71
  5788.6 1372.36  5821.4 1378.64  5854.1 1374.93  5859.4    1378    5880 1375.12
  5892.2 1378.35  5911.3 1375.65  5957.7    1376  6214.6 1387.23  6350.5 1387.86
#Mann= 3 ,-1 , 0
  4207.8     .05       0  4997.5     .05       0  5029.8     .05       0
Bank Sta=4997.5,5029.8
XS Rating Curve= 0 ,0
Exp/Cntr=0.3,0.1

Chan Stop Cuts=-1
Use User Specified Reach Order=0
Composite Channel Slope=5