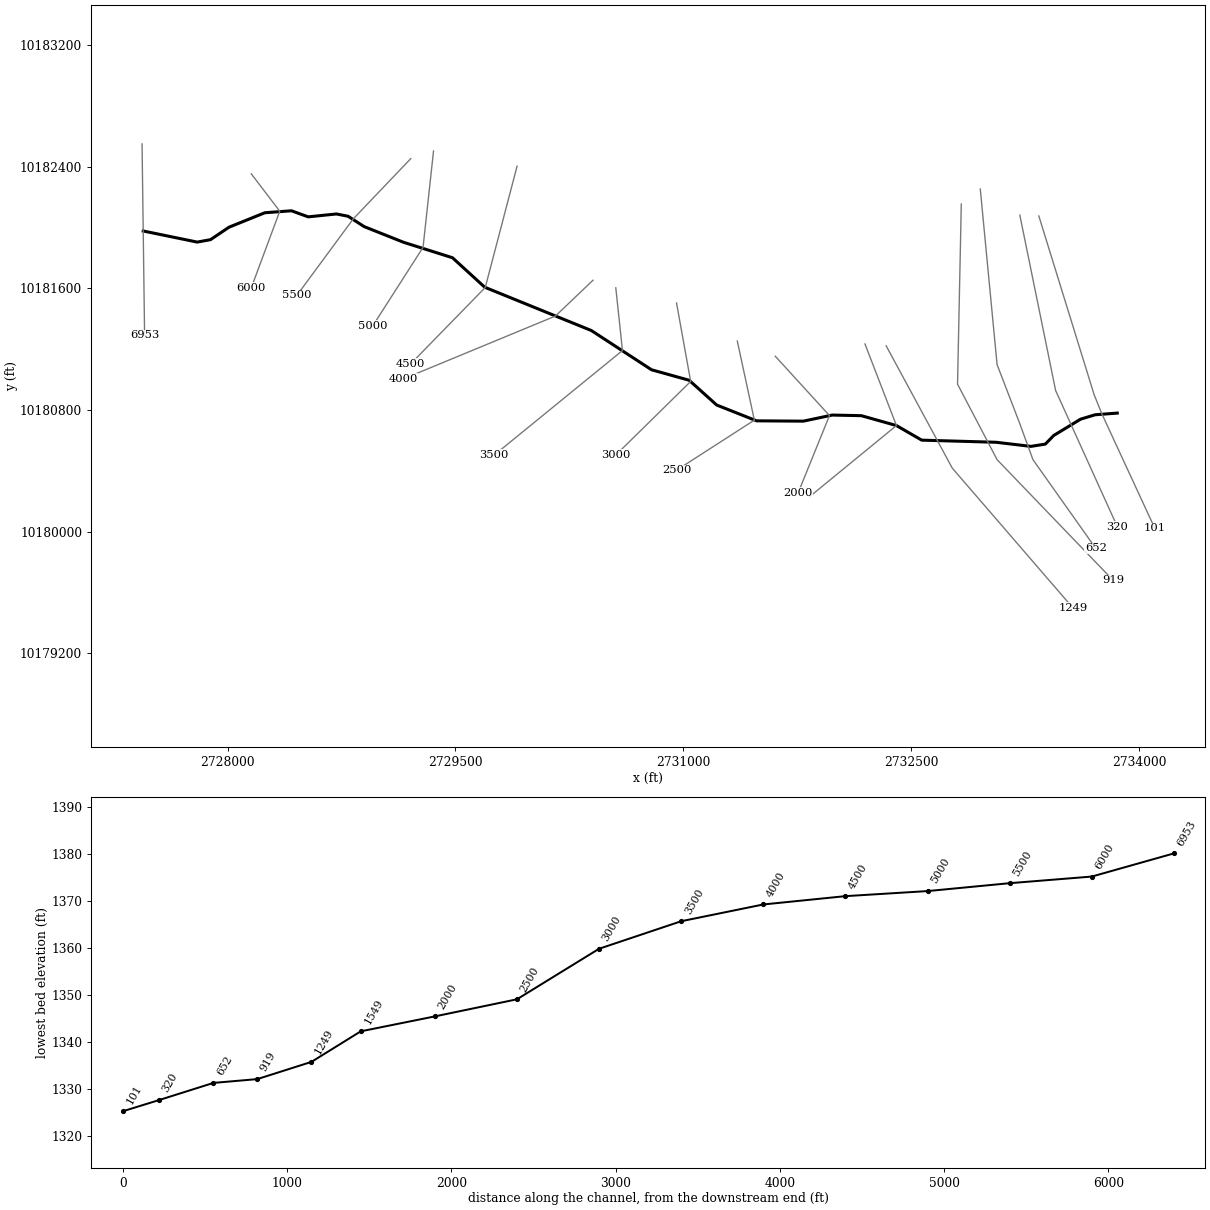
--- COLDSPRING CREEK.prj (project) ---

Proj Title=COLDSPRING CREEK Base Level Engineering
Current Plan=p01
Default Exp/Contr=0.3,0.1
English Units
Geom File=g01
Flow File=f01
Plan File=p01
Y Axis Title=Elevation
X Axis Title(PF)=Main Channel Distance
X Axis Title(XS)=Station
BEGIN DESCRIPTION:
COLDSPRING CREEK
END DESCRIPTION:
DSS Export Rating Curves= 0
DSS Export Rating Curve Sorted= 0
DSS Export Volume Flow Curves= 0
DXF OffsetX= 0
DXF OffsetY= 0
DXF ScaleX= 1
DXF ScaleY= 10

--- COLDSPRING CREEK.p01 (plan) ---

Plan Title=Multiple Run
Short Identifier=Multiple
Geom File=g01
Flow File=f01
Subcritical Flow
K Sum by GR= 0
Std Step Tol= 0.01
Critical Tol= 0.01
Num of Std Step Trials= 20
Max Error Tol= 0.3
Flow Tol Ratio= 0.001
Split Flow NTrial= 30
Split Flow Tol= 0.02
Split Flow Ratio= 0.02
Log Output Level= 0
Friction Slope Method= 1
Unsteady Friction Slope Method= 2
Unsteady Bridges Friction Slope Method= 1
Parabolic Critical Depth
Global Vel Dist=  1 , 1 , 1
Global Log Level= 0
CheckData=True
Encroach Param= -1, 0, 0, 0
BEGIN DESCRIPTION:
Multiple Run
END DESCRIPTION:

--- COLDSPRING CREEK.f01 (steady flow) ---

Flow Title=Multiple
Program Version=4.10
Number of Profiles= 7
Profile Names=10-year,25-year,50-year,1pct_min,100-year,1pct_plu,500-year
River Rch & RM=COLDSPRING CREEK,Reach-1         ,6953
    2847    5251    9243    6222   13449   29073   18702
River Rch & RM=COLDSPRING CREEK,Reach-1         ,2000
    2946    5450    9595    6424   13982   30430   19451
River Rch & RM=COLDSPRING CREEK,Reach-1         ,101
   15155   28536   45514   34078   65055  124191   85258
Boundary for River Rch & Prof#=COLDSPRING CREEK,Reach-1         , 1
Up Type= 0
Dn Type= 3
Dn Slope=0.005
Boundary for River Rch & Prof#=COLDSPRING CREEK,Reach-1         , 2
Up Type= 0
Dn Type= 3
Dn Slope=0.005
Boundary for River Rch & Prof#=COLDSPRING CREEK,Reach-1         , 3
Up Type= 0
Dn Type= 3
Dn Slope=0.005
Boundary for River Rch & Prof#=COLDSPRING CREEK,Reach-1         , 4
Up Type= 0
Dn Type= 3
Dn Slope=0.005
Boundary for River Rch & Prof#=COLDSPRING CREEK,Reach-1         , 5
Up Type= 0
Dn Type= 3
Dn Slope=0.005
Boundary for River Rch & Prof#=COLDSPRING CREEK,Reach-1         , 6
Up Type= 0
Dn Type= 3
Dn Slope=0.005
Boundary for River Rch & Prof#=COLDSPRING CREEK,Reach-1         , 7
Up Type= 0
Dn Type= 3
Dn Slope=0.005
DSS Import GetInterval= 0
DSS Import GetPeak= 0
DSS Import FillOption= 0

--- COLDSPRING CREEK.g01 (geometry) ---

Geom Title=Existing Conditions
Program Version=4.10

River Reach=COLDSPRING CREEK,Reach-1
Reach XY= 30
      2727444.25       10181977.      2727799.75       10181904.
      2727887.25       10181920.      2728009.25       10182002.
        2728245.       10182097.      2728420.25       10182110.
       2728530.5       10182070.        2728716.       10182089.
        2728793.       10182074.      2728898.75       10182006.
       2729157.5       10181903.       2729480.5       10181801.
        2729693.       10181607.        2730395.       10181322.
        2730791.       10181064.      2731038.75       10180995.
        2731220.       10180832.      2731482.75       10180728.
        2731791.       10180726.       2731980.5       10180766.
      2732172.25       10180762.       2732403.5       10180697.
        2732570.       10180601.      2733059.75       10180587.
        2733289.       10180560.      2733383.75       10180575.
       2733439.5       10180632.        2733616.       10180739.
      2733711.75       10180768.       2733857.5       10180779.

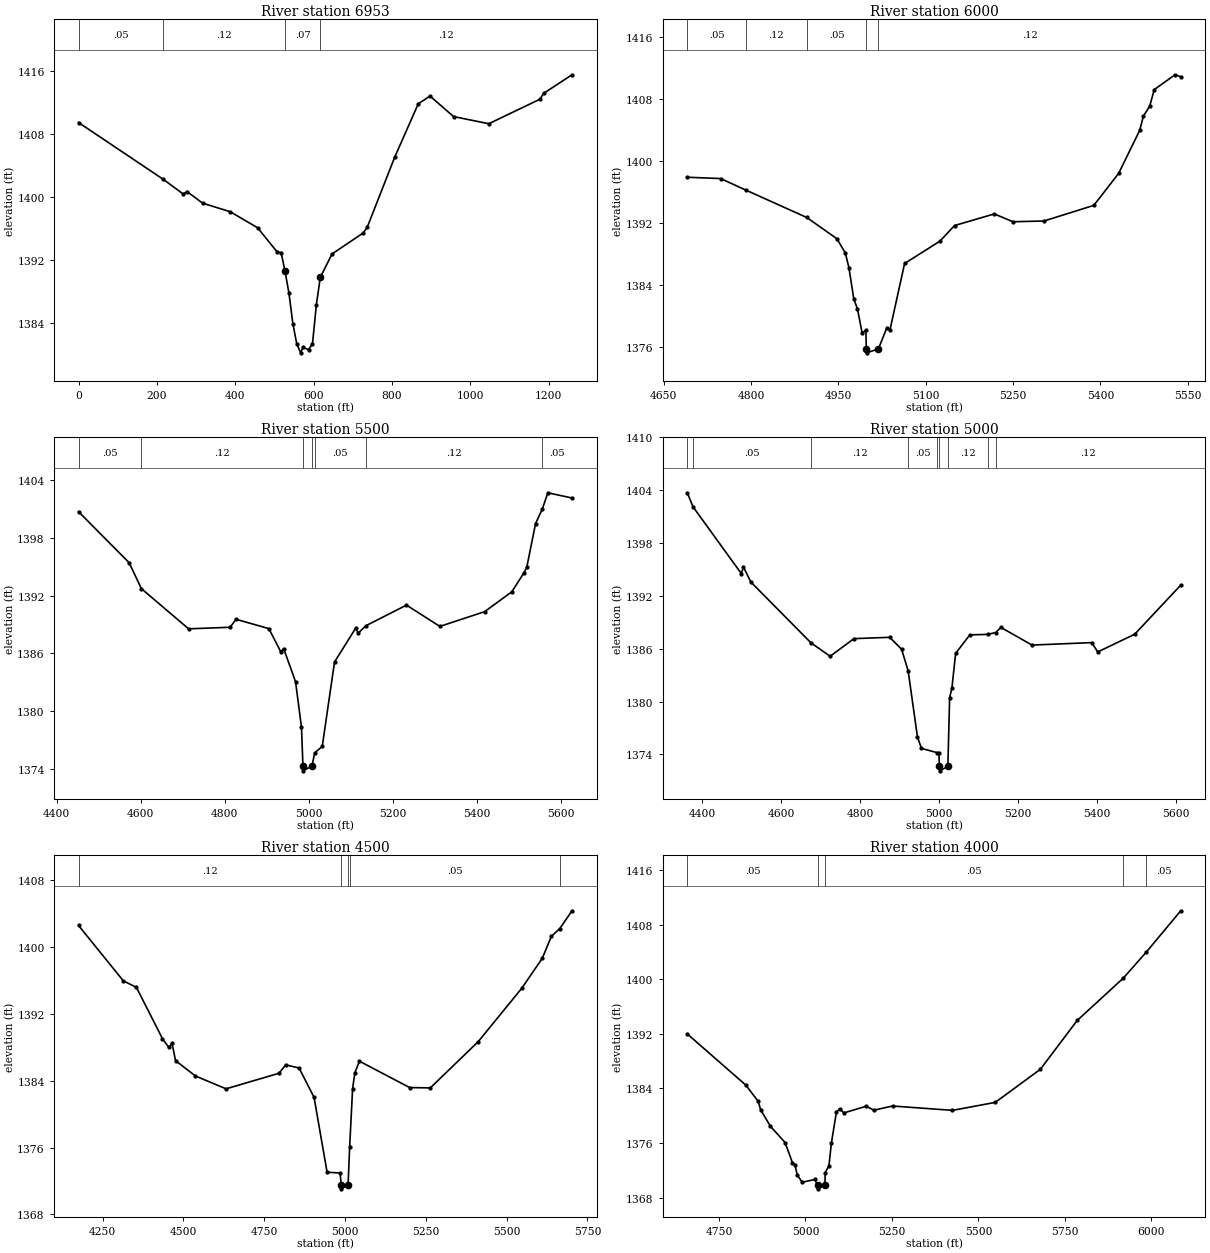
Type RM Length L Ch R = 1 ,6953    ,500,500,500
BEGIN DESCRIPTION:
COLDSPRING CREEK 13.0
END DESCRIPTION:
XS GIS Cut Line= 3
      2727436.58     10182549.92      2727444.25       10181977.
      2727453.34     10181290.89
#Sta/Elev= 30
       0 1409.48   216.8 1402.23   266.8 1400.39   276.8 1400.69   316.8 1399.21
   386.8 1398.13   456.8 1396.09   506.8 1393.01   516.9 1392.92   526.9 1390.56
   536.9 1387.76   546.9 1383.88   556.9 1381.28   566.9 1380.16   572.4 1380.85
   586.9 1380.57   596.9 1381.29   606.9  1386.3   616.9 1389.77   646.9 1392.75
   726.9 1395.44   736.9 1396.18   806.9 1405.09   866.9 1411.87   896.9 1412.85
   956.9 1410.24  1046.9 1409.33  1176.9 1412.44  1186.9  1413.2  1259.1 1415.56
#Mann= 4 ,-1 , 0
       0     .05       0   216.8     .12       0   526.9     .07       0
   616.9     .12       0
Bank Sta=526.9,616.9
XS Rating Curve= 0 ,0
Exp/Cntr=0.3,0.1

Type RM Length L Ch R = 1 ,6000    ,500,500,500
BEGIN DESCRIPTION:
COLDSPRING CREEK 12.0
END DESCRIPTION:
XS GIS Cut Line= 3
      2728155.68     10182353.11      2728343.15     10182107.23
       2728155.7     10181603.16
#Sta/Elev= 30
  4690.8 1397.87    4748  1397.7  4791.4 1396.21  4895.9 1392.68  4947.5 1389.95
  4962.1  1388.1  4968.3  1386.2  4976.6 1382.18  4982.9 1380.89  4991.1 1377.74
  4997.4 1378.19    4998 1375.73  4998.5 1375.23  5018.8 1375.73  5033.4 1378.47
  5038.8 1378.22  5063.8 1386.75  5124.5 1389.63  5149.5 1391.64  5217.8 1393.14
  5249.8 1392.13  5303.1 1392.23  5388.5 1394.24  5431.2 1398.36  5467.3 1403.91
  5473.8 1405.77  5484.5 1407.02  5492.3 1409.17    5528 1411.08  5537.8 1410.83
#Mann= 5 ,-1 , 0
  4690.8     .05       0  4791.4     .12       0  4895.9     .05       0
    4998     .05       0  5018.8     .12       0
Bank Sta=4998,5018.8
XS Rating Curve= 0 ,0
Exp/Cntr=0.3,0.1

Type RM Length L Ch R = 1 ,5500    ,500,500,500
BEGIN DESCRIPTION:
COLDSPRING CREEK 11.0
END DESCRIPTION:
XS GIS Cut Line= 3
      2729205.69     10182453.12      2728827.34     10182056.83
      2728455.68      10181553.1
#Sta/Elev= 30
  4452.1  1400.7  4572.4 1395.41  4601.6 1392.72  4713.9 1388.55  4812.7 1388.71
  4826.8 1389.54  4904.9 1388.57  4933.2 1386.17  4940.1  1386.5  4968.4 1383.06
  4982.5 1378.34    4986 1374.32  4986.5 1373.82  5007.4 1374.32    5014 1375.69
  5031.9 1376.35  5061.1 1385.11  5111.3 1388.61  5117.5  1388.1  5135.7 1388.87
  5232.3 1391.01  5311.7  1388.8  5418.2 1390.33  5482.9 1392.39  5512.2 1394.39
  5518.4 1394.92  5539.3 1399.46  5555.5 1400.98  5568.5 1402.66    5626 1402.12
#Mann= 7 ,-1 , 0
  4452.1     .05       0  4601.6     .12       0    4986     .07       0
  5007.4     .12       0    5014     .05       0  5135.7     .12       0
  5555.5     .05       0
Bank Sta=4986,5007.4
XS Rating Curve= 0 ,0
Exp/Cntr=0.3,0.1

Type RM Length L Ch R = 1 ,5000    ,500,500,500
BEGIN DESCRIPTION:
COLDSPRING CREEK 10.0
END DESCRIPTION:
XS GIS Cut Line= 3
      2729355.68     10182503.12      2729286.62     10181869.17
      2728955.66     10181353.07
#Sta/Elev= 30
  4362.3 1403.69  4376.8  1402.1  4499.5 1394.51  4504.5 1395.28  4523.3 1393.57
  4675.7 1386.67  4724.4 1385.14  4784.8 1387.14  4875.3 1387.29  4905.5 1385.94
  4922.2 1383.48  4945.7 1375.99  4955.8 1374.69  4996.4 1374.19    5000 1374.19
  5001.4 1372.64  5001.9 1372.14  5022.8 1372.64  5027.3 1380.43  5033.2 1381.58
  5042.5 1385.47  5078.5 1387.57  5123.8 1387.62  5143.7 1387.83  5157.4 1388.41
  5236.1 1386.41  5387.4 1386.69  5402.6 1385.63  5496.4 1387.64  5613.1 1393.21
#Mann= 9 ,-1 , 0
  4362.3     .12       0  4376.8     .05       0  4675.7     .12       0
  4922.2     .05       0  4996.4     .12       0  5001.4     .07       0
  5022.8     .12       0  5123.8     .05       0  5143.7     .12       0
Bank Sta=5001.4,5022.8
XS Rating Curve= 0 ,0
Exp/Cntr=0.3,0.1

Type RM Length L Ch R = 1 ,4500    ,500,500,500
BEGIN DESCRIPTION:
COLDSPRING CREEK 9.0
END DESCRIPTION:
XS GIS Cut Line= 3
      2729905.69     10182403.12      2729696.26     10181605.35
      2729205.67     10181103.09
#Sta/Elev= 30
  4175.2 1402.55  4313.9 1395.93  4354.3 1395.15    4435 1389.01  4454.4 1387.98
  4464.7 1388.44  4475.4 1386.39  4537.1 1384.55  4631.7 1383.02  4795.5 1384.88
  4816.2 1385.88  4857.6 1385.51    4904    1382  4944.3 1373.05  4984.7 1372.95
  4987.9 1371.56  4988.4 1371.06  5009.3 1371.56  5014.2  1376.1  5023.2 1383.02
  5030.3 1384.95  5044.5 1386.32  5199.9 1383.17  5263.7 1383.13  5412.1 1388.67
  5546.6 1395.04  5610.1 1398.62  5638.4 1401.26  5664.5 1402.19  5702.1 1404.31
#Mann= 5 ,-1 , 0
  4175.2     .12       0  4987.9     .07       0  5009.3     .12       0
  5014.2     .05       0  5664.5     .12       0
Bank Sta=4987.9,5009.3
XS Rating Curve= 0 ,0
Exp/Cntr=0.3,0.1

Type RM Length L Ch R = 1 ,4000    ,500,500,500
BEGIN DESCRIPTION:
COLDSPRING CREEK 8.0
END DESCRIPTION:
XS GIS Cut Line= 3
      2730405.68      10181653.1      2730158.32      10181417.5
      2729155.68     10181003.11
#Sta/Elev= 30
  4658.4 1391.99  4828.1 1384.47  4863.6 1382.09  4870.5 1380.87  4898.8 1378.46
  4941.3 1376.06  4962.4 1373.12  4969.6 1372.82  4976.5 1371.29  4990.7 1370.26
  5027.2 1370.66    5035 1369.79  5035.5 1369.29  5056.4 1369.79    5057 1371.68
  5067.8 1372.65  5075.1 1376.04  5089.4 1380.51    5099 1381.03  5111.1 1380.42
    5176  1381.4  5197.6 1380.81  5251.7 1381.43  5424.9 1380.79  5548.7 1381.96
  5679.1 1386.81  5785.6 1393.97  5918.7 1400.16  5984.9 1403.96  6084.9 1410.04
#Mann= 5 ,-1 , 0
  4658.4     .05       0    5035     .05       0  5056.4     .05       0
  5918.7     .12       0  5984.9     .05       0
Bank Sta=5035,5056.4
XS Rating Curve= 0 ,0
Exp/Cntr=0.3,0.1

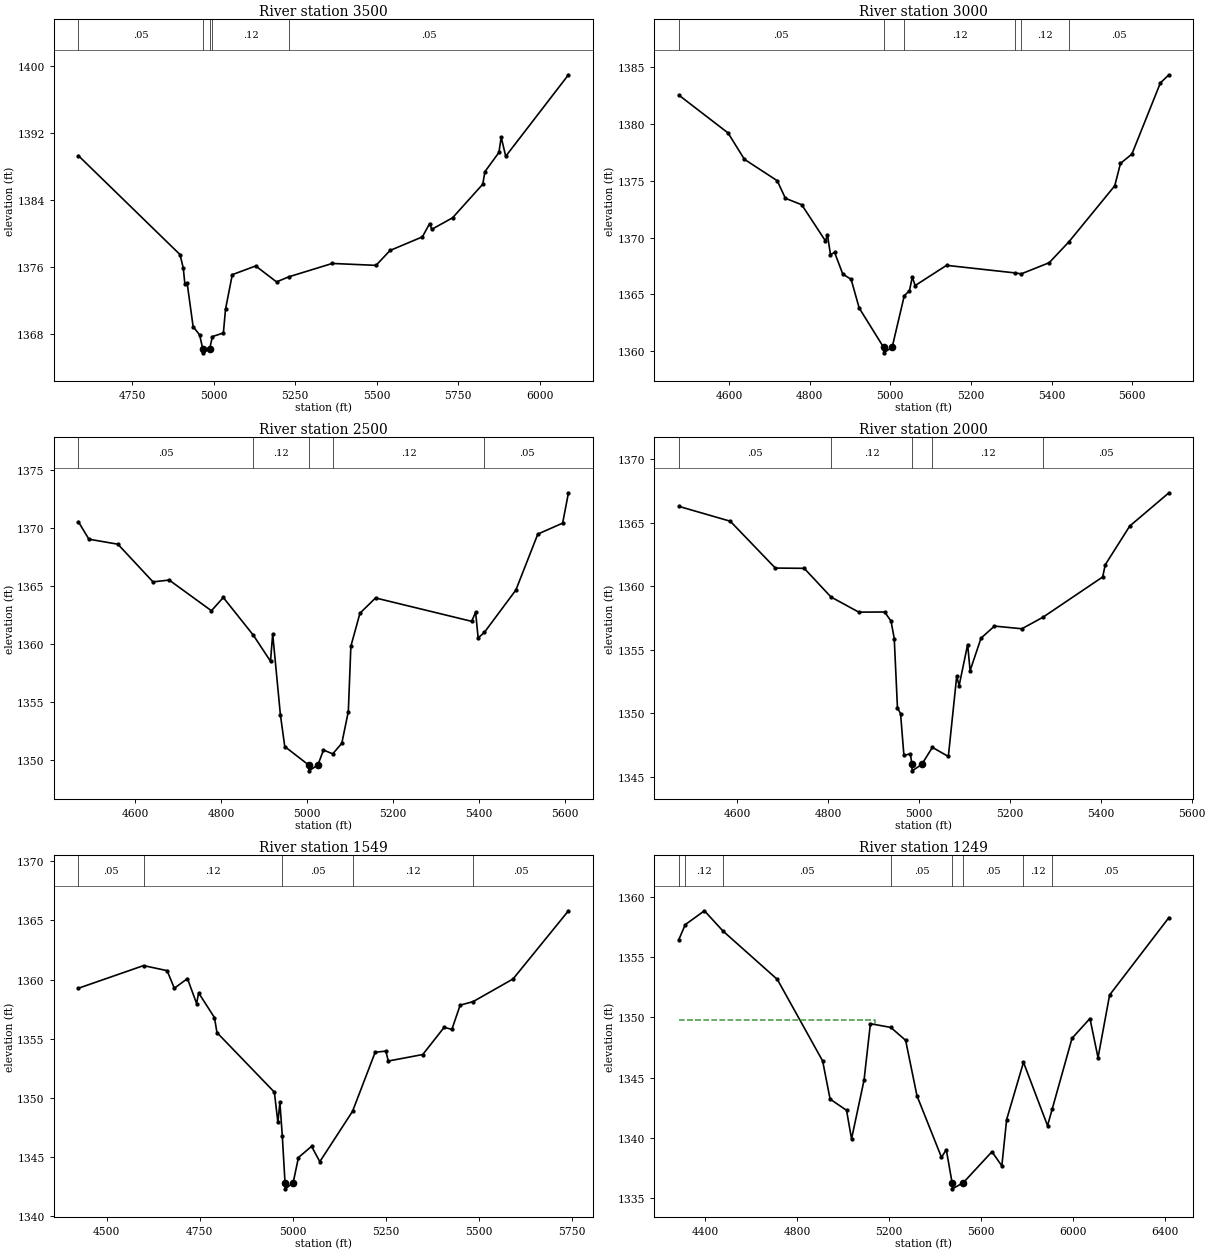
Type RM Length L Ch R = 1 ,3500    ,500,500,500
BEGIN DESCRIPTION:
COLDSPRING CREEK 7.0
END DESCRIPTION:
XS GIS Cut Line= 3
      2730555.68     10181603.13      2730599.65     10181190.47
      2729755.65     10180503.09
#Sta/Elev= 30
    4585 1389.26  4896.8 1377.45  4906.8 1375.85  4911.9  1373.9  4918.6 1374.08
    4937 1368.86  4957.1 1367.85  4966.5 1366.22    4967 1365.72    4988 1366.22
  4996.1 1367.66  5029.9 1368.09  5036.4 1370.92  5057.2 1375.05    5129 1376.09
  5192.9 1374.19  5231.1  1374.8  5363.9 1376.39  5498.1 1376.16  5541.2 1377.94
  5640.3 1379.56  5662.6 1381.15  5669.1 1380.46    5733 1381.84  5825.6 1385.85
  5832.1 1387.34  5875.2 1389.64  5882.1 1391.46    5896 1389.18  6088.5 1398.91
#Mann= 5 ,-1 , 0
    4585     .05       0  4966.5     .07       0    4988     .05       0
  4996.1     .12       0  5231.1     .05       0
Bank Sta=4966.5,4988
XS Rating Curve= 0 ,0
Exp/Cntr=0.3,0.1

Type RM Length L Ch R = 1 ,3000    ,500,500,500
BEGIN DESCRIPTION:
COLDSPRING CREEK 6.0
END DESCRIPTION:
XS GIS Cut Line= 3
      2730955.68     10181503.15      2731048.76     10180987.08
      2730555.69     10180503.11
#Sta/Elev= 30
  4475.6 1382.54  4597.6 1379.21  4638.2 1376.89  4719.5 1375.01  4739.8 1373.46
  4780.4 1372.89  4839.1 1369.71  4844.2 1370.21  4851.6  1368.5  4861.8  1368.7
  4882.1 1366.79  4902.8 1366.33  4922.7 1363.81  4983.1 1360.36  4983.6 1359.86
  5004.6 1360.36  5034.6 1364.89  5047.4 1365.32  5054.5 1366.53  5061.5 1365.78
  5139.4 1367.56  5310.2 1366.89  5324.6 1366.81  5393.9 1367.79  5442.8 1369.63
  5556.5 1374.56  5570.7 1376.53    5599 1377.35  5669.7 1383.62  5690.9 1384.33
#Mann= 6 ,-1 , 0
  4475.6     .05       0  4983.1     .05       0  5034.6     .12       0
  5310.2     .05       0  5324.6     .12       0  5442.8     .05       0
Bank Sta=4983.1,5004.6
XS Rating Curve= 0 ,0
Exp/Cntr=0.3,0.1

Type RM Length L Ch R = 1 ,2500    ,500,500,500
BEGIN DESCRIPTION:
COLDSPRING CREEK 5.0
END DESCRIPTION:
XS GIS Cut Line= 3
      2731355.68     10181253.11      2731468.07     10180732.61
      2730955.67      10180403.1
#Sta/Elev= 30
  4467.5 1370.51  4492.1 1369.01  4559.6 1368.58  4641.4 1365.34    4679  1365.5
  4777.5 1362.86  4805.1    1364  4875.1 1360.76  4915.1 1358.52  4920.2 1360.86
  4938.1 1353.93  4948.3 1351.19    5004  1349.6  5004.5  1349.1  5025.5  1349.6
  5038.5 1350.89  5060.1 1350.56  5081.2 1351.47  5096.4  1354.2  5102.3 1359.81
  5123.5 1362.65  5159.8 1363.96  5383.7 1361.95  5392.9 1362.73  5398.8 1360.52
  5413.3    1361  5486.7 1364.64  5537.8 1369.45  5595.6 1370.39  5609.2    1373
#Mann= 5 ,-1 , 0
  4467.5     .05       0  4875.1     .12       0    5004     .05       0
  5060.1     .12       0  5413.3     .05       0
Bank Sta=5004,5025.5
XS Rating Curve= 0 ,0
Exp/Cntr=0.3,0.1

Type RM Length L Ch R = 1 ,2000    ,451,451,451
BEGIN DESCRIPTION:
COLDSPRING CREEK 4.0
END DESCRIPTION:
XS GIS Cut Line= 3
      2731605.69     10181153.11      2731962.65     10180762.69
      2731755.69     10180253.12
#Sta/Elev= 30
    4471 1366.29  4584.2 1365.12  4683.4 1361.43    4747 1361.41    4806 1359.15
  4867.2 1357.96    4924 1357.97  4938.1 1357.26  4945.2 1355.88  4952.3 1350.42
  4959.1 1349.97  4966.5 1346.67  4980.7 1346.81  4984.1 1345.96  4984.6 1345.46
  5005.7 1345.96  5029.2 1347.31  5064.3 1346.59  5082.7  1352.9  5088.1 1352.18
  5106.8 1355.41  5112.2 1353.35  5136.3 1355.91  5165.8 1356.86  5226.2 1356.65
  5272.7 1357.56  5404.1 1360.73  5409.7 1361.69  5463.7 1364.74    5550 1367.36
#Mann= 5 ,-1 , 0
    4471     .05       0    4806     .12       0  4984.1     .05       0
  5029.2     .12       0  5272.7     .05       0
Bank Sta=4984.1,5005.7
XS Rating Curve= 0 ,0
Exp/Cntr=0.3,0.1

Type RM Length L Ch R = 1 ,1549    ,300,300,300
BEGIN DESCRIPTION:
COLDSPRING CREEK 3.5
END DESCRIPTION:
XS GIS Cut Line= 3
      2732196.18     10181233.97       2732403.5       10180697.
      2731830.65     10180228.08
#Sta/Elev= 30
  4424.4 1359.26  4599.5 1361.18  4662.8 1360.75    4682 1359.26  4717.3 1360.08
  4741.9 1357.97  4747.3 1358.87  4789.8 1356.78  4796.5 1355.51  4950.6 1350.47
  4960.2  1347.9  4965.5  1349.6    4972 1346.74  4979.3 1342.78  4979.8 1342.28
    5001 1342.78  5015.3 1344.93  5050.5 1345.88  5072.7 1344.58  5160.5 1348.84
  5221.3 1353.84    5250 1353.94  5256.5  1353.1  5349.1 1353.65  5406.5 1355.95
  5427.3 1355.78  5449.5 1357.83  5484.3 1358.13  5591.6 1360.05  5740.3 1365.82
#Mann= 5 ,-1 , 0
  4424.4     .05       0  4599.5     .12       0    4972     .05       0
  5160.5     .12       0  5484.3     .05       0
Bank Sta=4979.3,5001
XS Rating Curve= 0 ,0
Exp/Cntr=0.3,0.1

Type RM Length L Ch R = 1 ,1249    ,330,330,330
BEGIN DESCRIPTION:
Mapping XS fbf6f97c
END DESCRIPTION:
XS GIS Cut Line= 3
      2732335.69     10181221.82      2732771.07     10180417.07
      2733564.74     10179498.01
#Sta/Elev= 30
    4286 1356.44  4313.8 1357.68  4397.1 1358.83  4477.8 1357.15  4713.9 1353.14
  4910.7 1346.38  4943.1 1343.22  5014.5 1342.29  5036.3 1339.92  5090.6 1344.79
  5118.2 1349.47  5206.9 1349.16  5271.3 1348.09  5320.6 1343.49  5427.1 1338.39
  5447.9 1339.03  5473.2 1336.28  5474.2 1335.78  5521.4 1336.28  5646.5 1338.86
  5689.2 1337.68  5710.1 1341.52  5783.3 1346.27  5887.8 1341.02  5908.5 1342.42
  5994.2 1348.26  6072.1  1349.9  6107.2 1346.65  6157.5 1351.85  6415.3 1358.27
#Mann= 8 ,-1 , 0
    4286     .05       0  4313.8     .12       0  4477.8     .05       0
  5206.9     .05       0  5473.2     .05       0  5521.4     .05       0
  5783.3     .12       0  5908.5     .05       0
#XS Ineff= 2 , 0
         5138.43 1349.81
Permanent Ineff=
       F       F
Bank Sta=5473.2,5521.4
XS Rating Curve= 0 ,0
Exp/Cntr=0.3,0.1

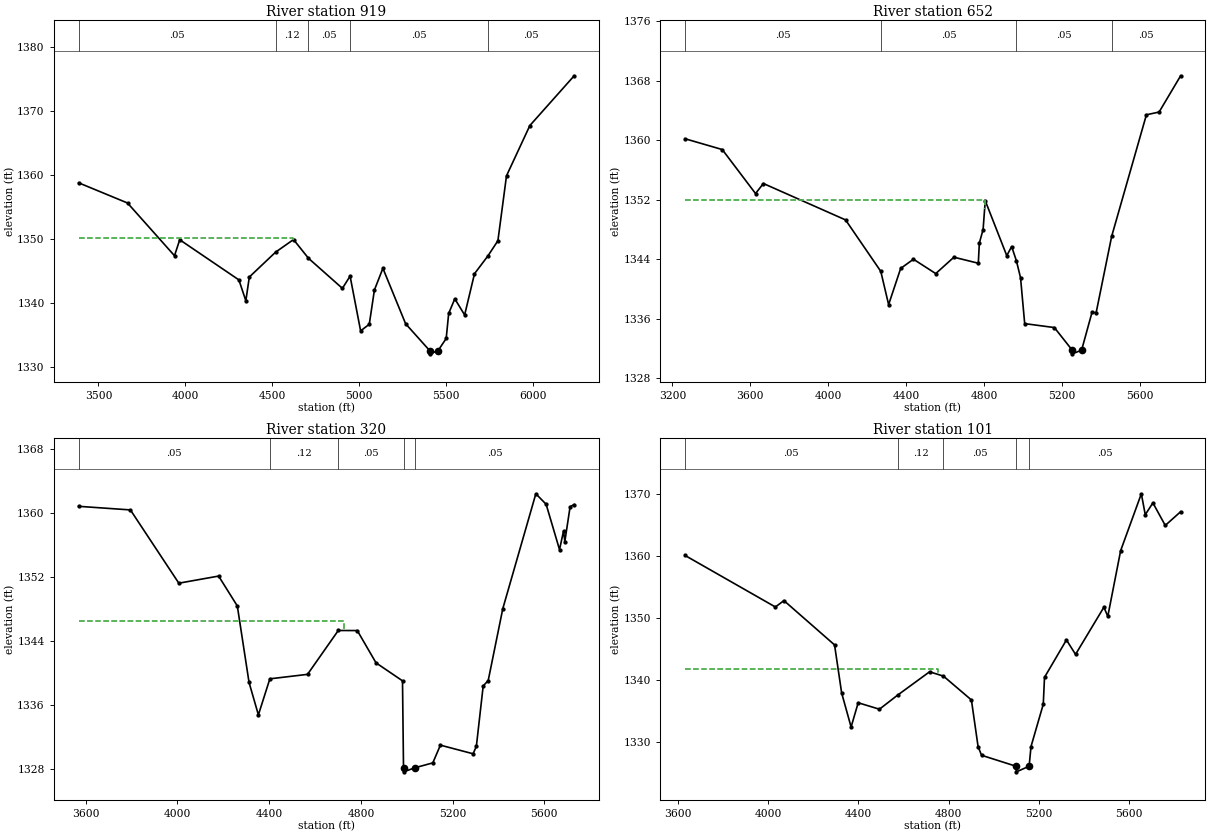
Type RM Length L Ch R = 1 ,919     ,267,267,267
BEGIN DESCRIPTION:
Mapping XS 6fb7025c
END DESCRIPTION:
XS GIS Cut Line= 4
      2732830.47     10182154.11      2732805.79     10180969.15
       2733066.2     10180472.62      2733830.71     10179678.09
#Sta/Elev= 30
  3386.4 1358.78  3667.5 1355.63  3937.5 1347.41  3967.5  1349.9  4307.6 1343.64
  4347.6 1340.39  4367.6 1344.09  4518.3 1347.96  4621.6 1349.93  4707.7 1347.01
  4902.7 1342.32  4946.8 1344.23  5007.3 1335.69  5057.1 1336.72  5086.6 1342.06
  5135.4 1345.45    5266  1336.8  5404.5 1332.61  5405.5 1332.11  5452.7 1332.61
  5499.3 1334.51  5513.5 1338.41  5548.7 1340.69  5605.3 1338.17  5661.9  1344.6
  5739.9 1347.41  5796.5 1349.75  5845.9 1359.87  5980.2 1367.71  6234.9 1375.47
#Mann= 5 ,-1 , 0
  3386.4     .05       0  4518.3     .12       0  4707.7     .05       0
  4946.8     .05       0  5739.9     .05       0
#XS Ineff= 2 , 0
         4619.31 1350.18
Permanent Ineff=
       F       F
Bank Sta=5404.5,5452.7
XS Rating Curve= 0 ,0
Exp/Cntr=0.3,0.1

Type RM Length L Ch R = 1 ,652     ,332,332,332
BEGIN DESCRIPTION:
Mapping XS 03bdecb6
END DESCRIPTION:
XS GIS Cut Line= 5
      2732955.48     10182253.08       2733066.2     10181097.62
      2733212.04     10180719.15      2733302.32     10180472.62
      2733715.49     10179889.32
#Sta/Elev= 30
  3265.6 1360.19  3456.4 1358.74  3627.2 1352.83  3667.4 1354.18  4089.3 1349.29
  4270.1 1342.38  4310.3 1337.91  4372.1 1342.77  4437.7 1344.01  4552.2 1342.08
  4645.5 1344.28  4770.7 1343.47    4776 1346.18  4795.3    1348  4806.3 1351.87
  4916.8 1344.49  4941.9 1345.71  4966.2  1343.8  4987.5 1341.52  5008.8 1335.36
  5161.1 1334.83  5252.6  1331.8  5253.6  1331.3    5301  1331.8  5354.3 1336.87
  5375.7 1336.84  5455.2 1347.08  5633.6 1363.41  5698.8 1363.78  5809.3 1368.65
#Mann= 4 ,-1 , 0
  3265.6     .05       0  4270.1     .05       0  4966.2     .05       0
  5455.2     .05       0
#XS Ineff= 2 , 0
         4803.28 1351.97
Permanent Ineff=
       F       F
Bank Sta=5252.6,5301
XS Rating Curve= 0 ,0
Exp/Cntr=0.3,0.1

Type RM Length L Ch R = 1 ,320     ,219,219,219
BEGIN DESCRIPTION:
Mapping XS dfe58043
END DESCRIPTION:
XS GIS Cut Line= 3
      2733215.88     10182081.25      2733451.62     10180927.49
      2733857.85     10180031.69
#Sta/Elev= 30
    3569 1360.87  3794.8 1360.42    4006 1351.25  4179.5 1352.14  4261.1  1348.4
  4312.2 1338.83    4353 1334.77    4403 1339.28  4567.3 1339.84  4701.4 1345.33
  4784.3 1345.32    4866 1341.28  4981.5 1339.03  4985.9 1328.14  4986.9 1327.64
  5034.3 1328.14  5113.7 1328.76  5146.7 1330.98  5289.4  1329.9  5303.6 1330.83
  5333.4 1338.39  5355.3 1339.07    5419 1348.07    5563 1362.44  5607.9 1361.13
  5666.3 1355.45  5683.9 1357.79  5689.4 1356.46  5712.5 1360.83  5730.2 1361.09
#Mann= 5 ,-1 , 0
    3569     .05       0    4403     .12       0  4701.4     .05       0
  4985.9     .05       0  5034.3     .05       0
#XS Ineff= 2 , 0
         4724.95 1346.56
Permanent Ineff=
       F       F
Bank Sta=4985.9,5034.3
XS Rating Curve= 0 ,0
Exp/Cntr=0.3,0.1

Type RM Length L Ch R = 1 ,101     ,0,0,0
BEGIN DESCRIPTION:
COLDSPRING CREEK 3.0
END DESCRIPTION:
XS GIS Cut Line= 4
       2733340.9     10182075.99      2733705.47     10180898.92
       2733756.5       10180773.      2734104.41      10180021.2
#Sta/Elev= 30
  3631.9 1360.13  4032.1 1351.83    4070 1352.86  4294.4 1345.72  4325.8 1337.98
  4367.7 1332.49  4399.1  1336.4  4493.3 1335.36    4574 1337.63  4715.6 1341.39
  4777.1 1340.69    4901 1336.85  4930.5 1329.35  4945.9 1327.94  5098.9 1326.17
  5100.2 1325.27  5156.8 1326.17  5165.2 1329.35  5219.5 1336.16    5225  1340.5
  5322.2 1346.52  5362.6 1344.19  5488.2 1351.79  5505.6 1350.33  5562.5 1360.91
  5654.2 1370.07  5671.6  1366.7  5705.5  1368.6  5760.2 1364.97  5828.4 1367.18
#Mann= 5 ,-1 , 0
  3631.9     .05       0    4574     .12       0  4777.1     .05       0
  5098.9     .05       0  5156.8     .05       0
#XS Ineff= 2 , 0
         4752.28 1341.76
Permanent Ineff=
       F       F
Bank Sta=5098.9,5156.8
XS Rating Curve= 0 ,0
Exp/Cntr=0.3,0.1
Stream Node=COLDSPRING CREEK,Reach-1         , 0 , 0 ,Upstream end
Stream Node=COLDSPRING CREEK,Reach-1         , 0 , 1 ,Downstream end

Chan Stop Cuts=-1
Use User Specified Reach Order=0
Composite Channel Slope=5