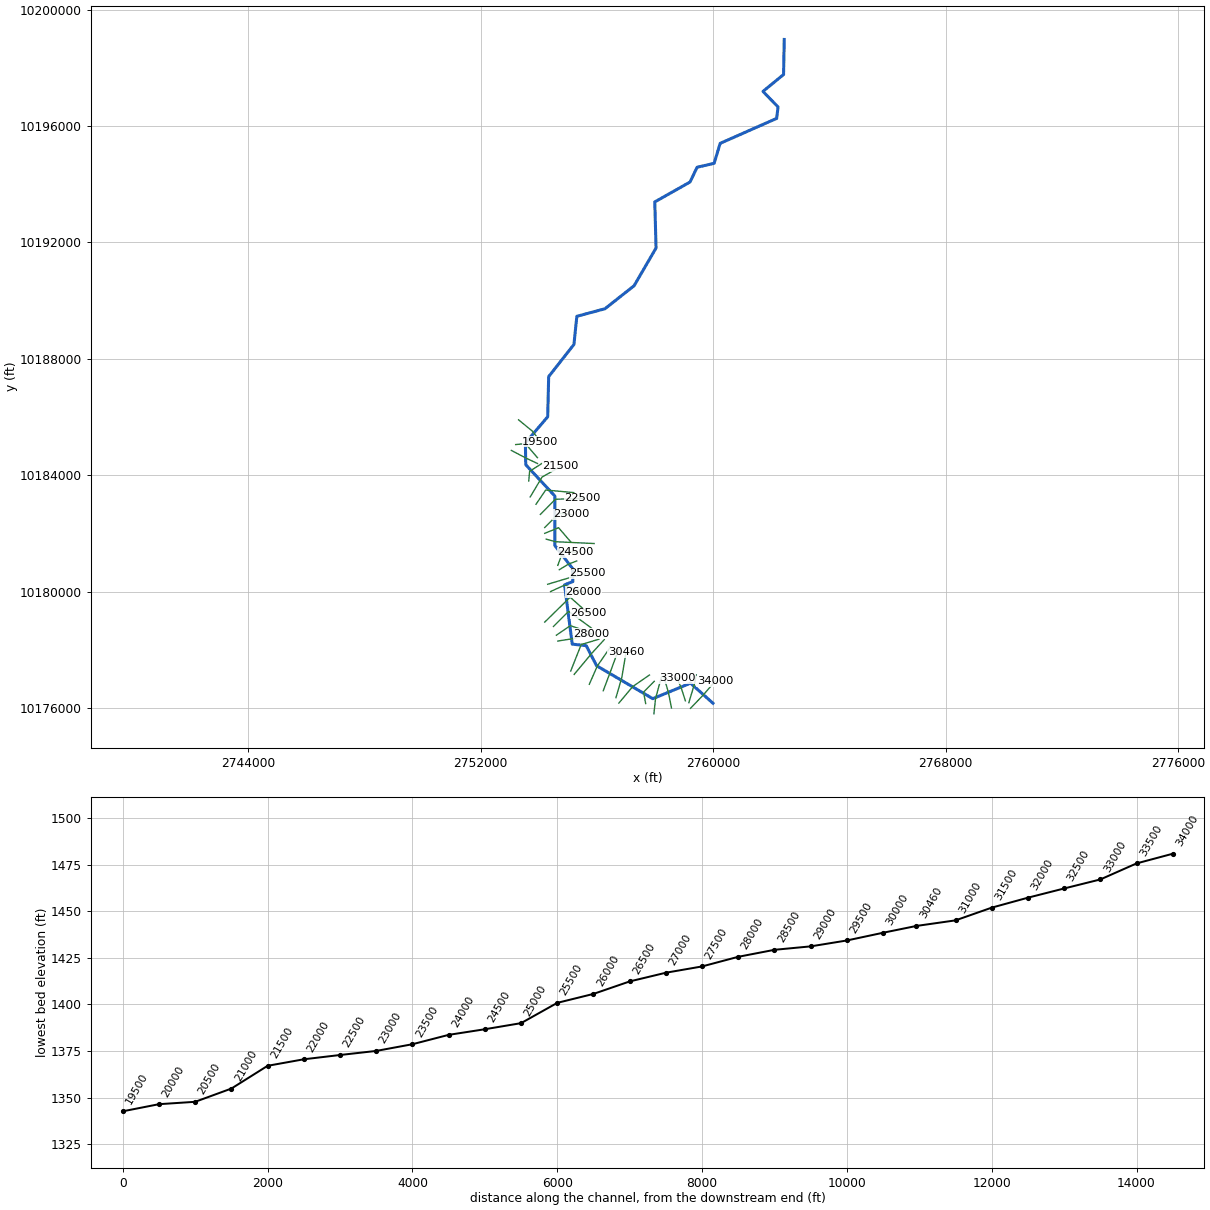
--- COTTONWOOD CREEK.prj (project) ---

Proj Title=COTTONWOOD CREEK Base Level Engineering
Current Plan=p01
Default Exp/Contr=0.3,0.1
English Units
Geom File=g01
Flow File=f01
Plan File=p01
BEGIN DESCRIPTION:
COTTONWOOD CREEK
END DESCRIPTION:

--- COTTONWOOD CREEK.p01 (plan) ---

Plan Title=Multiple Run
Short Identifier=Multiple
Geom File=g01
Flow File=f01
Subcritical Flow
K Sum by GR= 0
Std Step Tol= 0.01
Critical Tol= 0.01
Num of Std Step Trials= 20
Max Error Tol= 0.3
Flow Tol Ratio= 0.001
Split Flow NTrial= 30
Split Flow Tol= 0.02
Split Flow Ratio= 0.02
Log Output Level= 0
Friction Slope Method= 1
Unsteady Friction Slope Method= 2
Unsteady Bridges Friction Slope Method= 1
Parabolic Critical Depth
Global Vel Dist=  1 , 1 , 1
Global Log Level= 0
CheckData=True
Encroach Param= -1, 0, 0, 0
BEGIN DESCRIPTION:
Multiple Run
END DESCRIPTION:

--- COTTONWOOD CREEK.f01 (steady flow) ---

Flow Title=Multiple
Number of Profiles=7
Profile Names=10-year,25-year,50-year,1pct_min,100-year,1pct_plu,500-year
River Rch & RM= COTTONWOOD CREEK,Reach-1,34000
     360     570     925     778    1245    1991    1731
River Rch & RM= COTTONWOOD CREEK,Reach-1,31000
     637    1051    1618    1228    2208    3971    3052
River Rch & RM= COTTONWOOD CREEK,Reach-1,25500
     804    1346    2171    1635    2998    5495    4150
River Rch & RM= COTTONWOOD CREEK,Reach-1,23000
    1086    1863    3034    2192    4242    8208    5888
River Rch & RM= COTTONWOOD CREEK,Reach-1,17500
    1347    2351    3727    2595    5240   10580    7265
River Rch & RM= COTTONWOOD CREEK,Reach-1,12000
    1565    2761    4320    2958    6093   12551    8429
River Rch & RM= COTTONWOOD CREEK,Reach-1,8000
    1904    3413    5144    3414    7279   15520   10038
River Rch & RM= COTTONWOOD CREEK,Reach-1,500
    1923    3451    5179    3428    7328   15668   10105
Boundary for River Rch & Prof#=COTTONWOOD CREEK,Reach-1,1
Up Type=0
Dn Type=3
Dn Slope=0.005
Boundary for River Rch & Prof#=COTTONWOOD CREEK,Reach-1,2
Up Type=0
Dn Type=3
Dn Slope=0.005
Boundary for River Rch & Prof#=COTTONWOOD CREEK,Reach-1,3
Up Type=0
Dn Type=3
Dn Slope=0.005
Boundary for River Rch & Prof#=COTTONWOOD CREEK,Reach-1,4
Up Type=0
Dn Type=3
Dn Slope=0.005
Boundary for River Rch & Prof#=COTTONWOOD CREEK,Reach-1,5
Up Type=0
Dn Type=3
Dn Slope=0.005
Boundary for River Rch & Prof#=COTTONWOOD CREEK,Reach-1,6
Up Type=0
Dn Type=3
Dn Slope=0.005
Boundary for River Rch & Prof#=COTTONWOOD CREEK,Reach-1,7
Up Type=0
Dn Type=3
Dn Slope=0.005

--- COTTONWOOD CREEK.g01 (geometry) ---

Geom Title=Existing Conditions

River Reach=COTTONWOOD CREEK,Reach-1
Reach XY= 30
      2759992.75     10176165.00      2759221.00     10176856.00
      2757922.00     10176322.00      2755990.00     10177454.00
      2755632.25     10178144.00      2755151.50     10178196.00
      2754888.00     10180235.00      2755172.50     10180347.00
      2755160.00     10180797.00      2754553.75     10181585.00
      2754553.75     10183285.00      2753552.75     10184360.00
      2753540.25     10185110.00      2754307.75     10186009.00
      2754341.25     10187388.00      2755210.00     10188494.00
      2755310.00     10189460.00      2756278.25     10189721.00
      2757278.75     10190510.00      2758035.00     10191807.00
      2757991.25     10193391.00      2759203.75     10194075.00
      2759447.50     10194582.00      2760031.75     10194716.00
      2760241.25     10195404.00      2762183.50     10196261.00
      2762231.75     10196654.00      2761713.00     10197188.00
      2762421.50     10197769.00      2762444.25     10198973.00

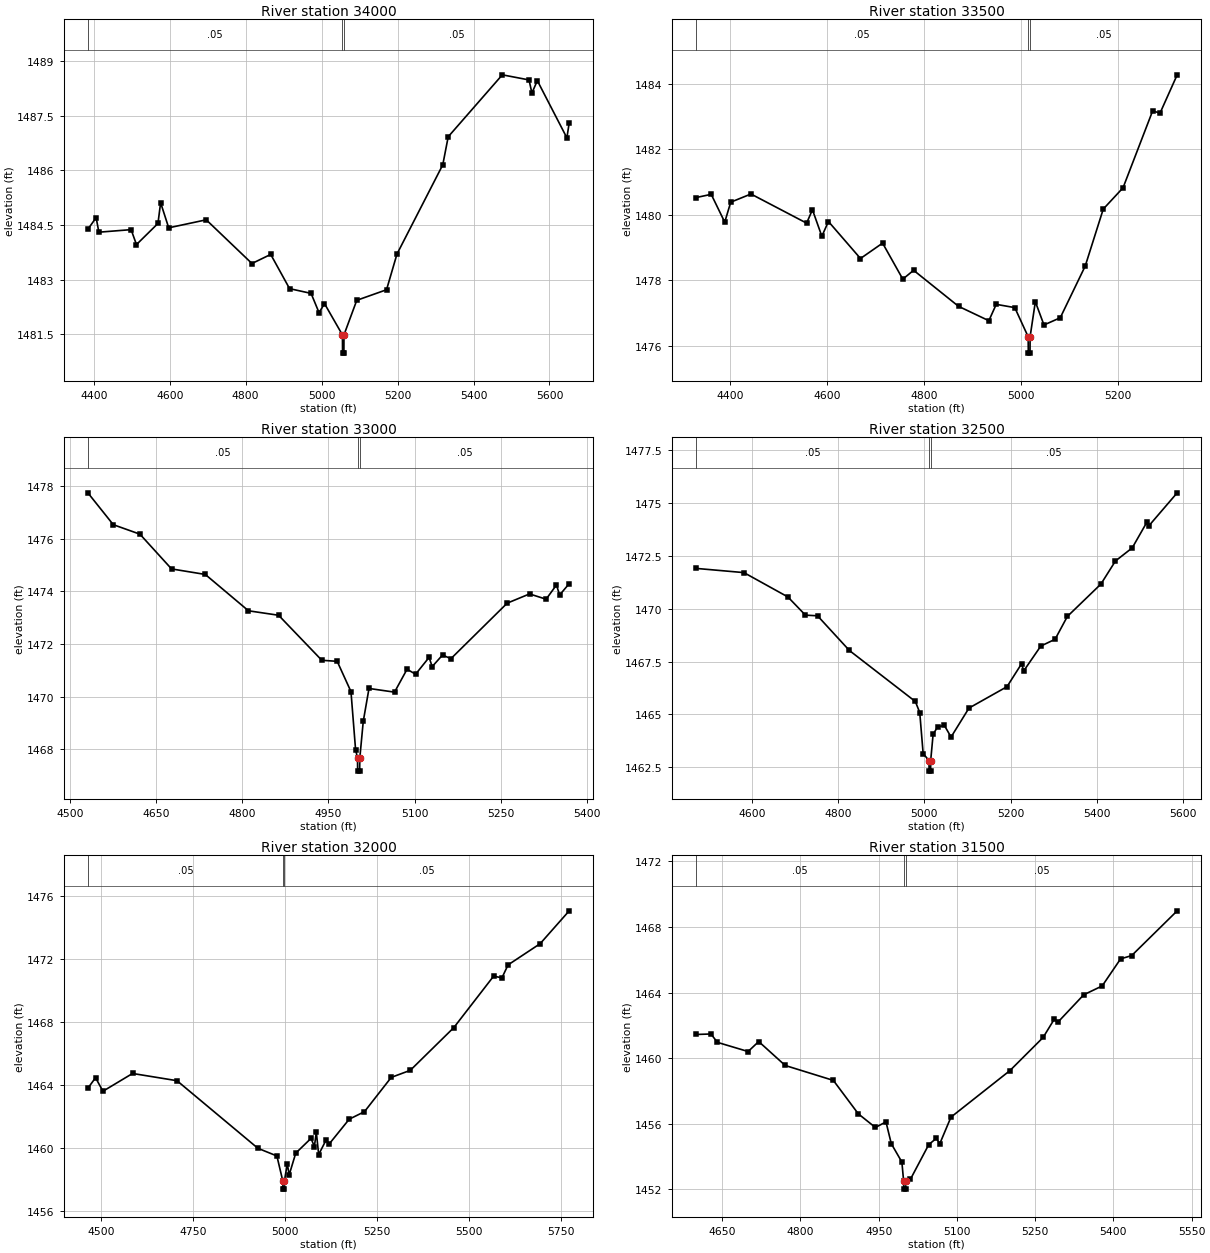
Type RM Length L Ch R = 1,34000,500,500,500
BEGIN DESCRIPTION:
COTTONWOOD CREEK 68.0
END DESCRIPTION:
XS GIS Cut Line= 3
      2759218.14     10175989.77      2759645.25     10176433.10
      2760071.50     10176926.33
#Sta/Elev= 30
  4384.4 1484.38  4406.2 1484.70  4413.4 1484.30  4498.3 1484.37  4512.4 1483.96
  4569.0 1484.54  4576.0 1485.11  4597.3 1484.42  4696.1 1484.64  4816.5 1483.44
  4865.9 1483.69  4915.6 1482.75  4972.2 1482.62  4993.2 1482.09  5007.5 1482.34
  5054.8 1481.48  5055.1 1480.98  5058.6 1480.98  5058.8 1481.48  5092.5 1482.43
  5170.9 1482.72  5198.4 1483.70  5319.0 1486.15  5333.3 1486.92  5475.8 1488.62
  5546.1 1488.48  5553.7 1488.12  5568.0 1488.46  5645.8 1486.89  5651.9 1487.30
#Mann=3,-1,0
  4384.4    0.05       0  5054.8   0.035       0  5058.8    0.05       0
Bank Sta=5054.8,5058.8
Exp/Cntr=0.3,0.1

Type RM Length L Ch R = 1,33500,500,500,500
BEGIN DESCRIPTION:
COTTONWOOD CREEK 67.0
END DESCRIPTION:
XS GIS Cut Line= 3
      2759162.60     10176184.23      2759355.37     10176826.11
      2759417.51     10177142.77
#Sta/Elev= 30
  4329.8 1480.53  4361.5 1480.63  4389.4 1479.78  4401.7 1480.39  4443.5 1480.64
  4558.3 1479.75  4570.3 1480.16  4589.7 1479.35  4603.3 1479.80  4669.4 1478.67
  4715.0 1479.14  4756.7 1478.04  4779.0 1478.31  4871.6 1477.21  4934.2 1476.77
  4949.4 1477.27  4987.7 1477.17  5015.3 1476.28  5015.6 1475.78  5019.1 1475.78
  5019.3 1476.28  5030.1 1477.35  5047.9 1476.64  5081.5 1476.86  5133.0 1478.44
  5170.2 1480.18  5211.0 1480.83  5272.1 1483.18  5287.3 1483.11  5322.7 1484.28
#Mann=3,-1,0
  4329.8    0.05       0  5015.3   0.035       0  5019.3    0.05       0
Bank Sta=5015.3,5019.3
Exp/Cntr=0.3,0.1

Type RM Length L Ch R = 1,33000,500,500,500
BEGIN DESCRIPTION:
COTTONWOOD CREEK 66.0
END DESCRIPTION:
XS GIS Cut Line= 3
      2759044.52     10176246.77      2758900.73     10176693.29
      2758753.45     10177032.16
#Sta/Elev= 30
  4530.9 1477.74  4575.2 1476.53  4621.6 1476.17  4676.7 1474.85  4735.5 1474.64
  4810.7 1473.26  4863.2 1473.09  4938.5 1471.38  4965.3 1471.34  4989.3 1470.19
  4997.3 1467.99  5000.7 1467.67  5000.9 1467.17  5004.4 1467.17  5004.7 1467.67
  5010.7 1469.06  5020.7 1470.31  5065.2 1470.17  5087.0 1471.04  5101.9 1470.85
  5125.4 1471.49  5130.8 1471.14  5148.8 1471.58  5163.4 1471.44  5261.5 1473.55
  5300.4 1473.90  5329.3 1473.70  5347.3 1474.24  5352.8 1473.86  5369.5 1474.29
#Mann=3,-1,0
  4530.9    0.05       0  5000.7    0.05       0  5004.7    0.05       0
Bank Sta=5000.7,5004.7
Exp/Cntr=0.3,0.1

Type RM Length L Ch R = 1,32500,500,500,500
BEGIN DESCRIPTION:
COTTONWOOD CREEK 65.0
END DESCRIPTION:
XS GIS Cut Line= 3
      2758565.36     10176003.72      2758463.57     10176523.64
      2758301.49     10177086.99
#Sta/Elev= 30
  4470.2 1471.90  4581.7 1471.70  4683.6 1470.55  4724.3 1469.69  4752.3 1469.66
  4826.2 1468.02  4979.1 1465.61  4989.3 1465.09  4997.2 1463.15  5010.7 1462.82
  5011.0 1462.32  5014.5 1462.32  5014.7 1462.82  5020.3 1464.06  5030.7 1464.41
  5046.4 1464.48  5061.9 1463.93  5103.5 1465.30  5191.6 1466.31  5225.3 1467.39
  5230.5 1467.06  5270.0 1468.23  5303.1 1468.55  5331.6 1469.63  5409.4 1471.16
  5443.1 1472.25  5482.0 1472.87  5515.6 1474.07  5520.9 1473.92  5586.2 1475.47
#Mann=3,-1,0
  4470.2    0.05       0  5010.7    0.03       0  5014.7    0.05       0
Bank Sta=5010.7,5014.7
Exp/Cntr=0.3,0.1

Type RM Length L Ch R = 1,32000,500,500,500
BEGIN DESCRIPTION:
COTTONWOOD CREEK 64.0
END DESCRIPTION:
XS GIS Cut Line= 3
      2757961.21     10175802.33      2758018.06     10176334.30
      2758224.84     10177079.13
#Sta/Elev= 30
  4465.0 1463.79  4485.9 1464.46  4506.0 1463.60  4586.5 1464.73  4707.2 1464.27
  4927.0 1459.97  4978.7 1459.48  4994.9 1457.87  4995.1 1457.37  4998.6 1457.37
  4998.9 1457.87  5006.9 1458.97  5012.1 1458.28  5029.9 1459.66  5071.4 1460.60
  5080.6 1460.08  5085.8 1461.00  5092.2 1459.57  5112.9 1460.52  5120.0 1460.22
  5175.2 1461.82  5216.7 1462.30  5289.4 1464.48  5341.2 1464.93  5459.5 1467.65
  5567.5 1470.92  5590.3 1470.82  5606.9 1471.64  5694.1 1472.99  5773.0 1475.08
#Mann=3,-1,0
  4465.0    0.05       0  4994.9    0.03       0  4998.9    0.05       0
Bank Sta=4994.9,4998.9
Exp/Cntr=0.3,0.1

Type RM Length L Ch R = 1,31500,500,500,500
BEGIN DESCRIPTION:
COTTONWOOD CREEK 63.0
END DESCRIPTION:
XS GIS Cut Line= 3
      2757677.63     10176154.60      2757605.10     10176548.48
      2757972.93     10176919.29
#Sta/Elev= 30
  4599.5 1461.45  4628.5 1461.48  4640.8 1460.97  4699.7 1460.41  4720.0 1461.02
  4770.8 1459.56  4863.1 1458.65  4911.0 1456.61  4943.7 1455.78  4964.0 1456.12
  4974.2 1454.79  4994.5 1453.67  4997.8 1452.52  4998.1 1452.02  5001.6 1452.02
  5001.8 1452.52  5010.7 1452.61  5046.1 1454.74  5060.3 1455.11  5067.3 1454.80
  5088.6 1456.41  5201.7 1459.25  5265.3 1461.27  5286.6 1462.38  5293.6 1462.20
  5343.1 1463.87  5378.5 1464.41  5413.8 1466.06  5435.0 1466.26  5522.3 1468.99
#Mann=3,-1,0
  4599.5    0.05       0  4997.8    0.03       0  5001.8    0.05       0
Bank Sta=4997.8,5001.8
Exp/Cntr=0.3,0.1

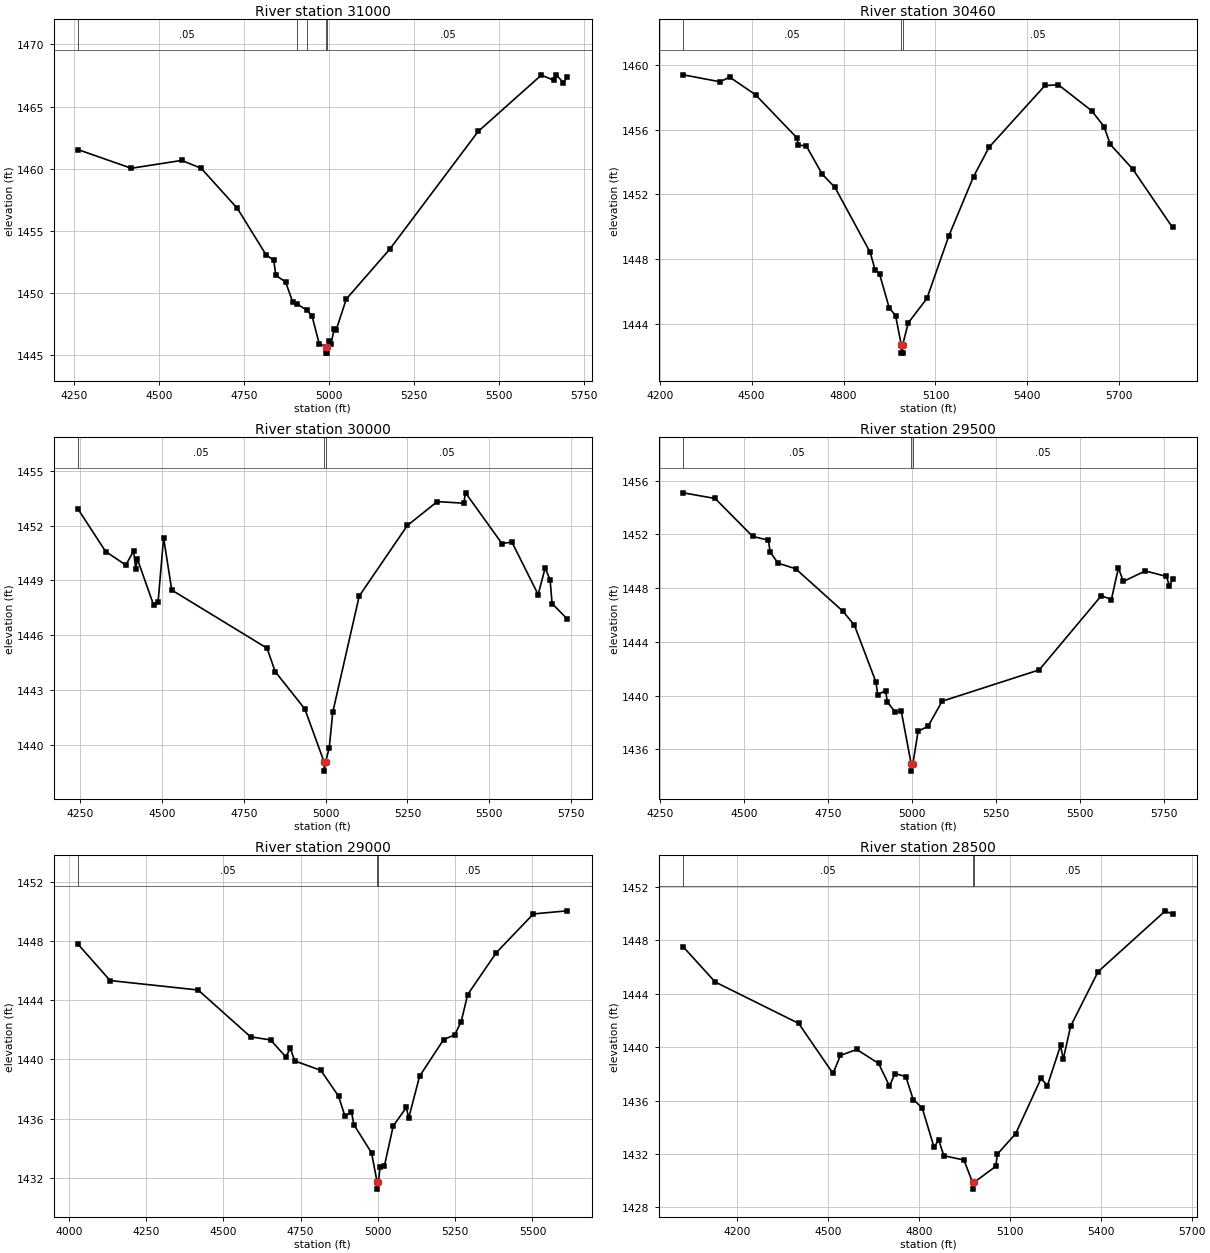
Type RM Length L Ch R = 1,31000,540,540,540
BEGIN DESCRIPTION:
COTTONWOOD CREEK 62.0
END DESCRIPTION:
XS GIS Cut Line= 3
      2756756.81     10176171.76      2757231.52     10176737.74
      2757808.42     10177135.61
#Sta/Elev= 30
  4261.3 1461.55  4418.0 1460.05  4566.4 1460.68  4623.6 1460.05  4730.3 1456.82
  4814.9 1453.08  4837.0 1452.67  4843.5 1451.44  4872.1 1450.91  4892.9 1449.31
  4904.4 1449.16  4935.6 1448.63  4950.1 1448.15  4971.0 1445.94  4990.9 1445.69
  4991.2 1445.19  4994.9 1445.19  4995.2 1445.69  4999.3 1446.19  5005.9 1445.93
  5014.7 1447.12  5020.8 1447.04  5050.5 1449.53  5179.0 1453.56  5438.7 1463.01
  5624.6 1467.54  5661.0 1467.12  5668.5 1467.56  5689.5 1466.93  5700.8 1467.37
#Mann=5,-1,0
  4261.3    0.05       0  4904.4    0.12       0  4935.6    0.05       0
  4990.9    0.05       0  4995.2    0.05       0
Bank Sta=4990.9,4995.2
Exp/Cntr=0.3,0.1

Type RM Length L Ch R = 1,30460,460,460,460
BEGIN DESCRIPTION:
COTTONWOOD CREEK 61.0
END DESCRIPTION:
XS GIS Cut Line= 3
      2756655.65     10176357.85      2756857.50     10177052.00
      2757002.88     10177913.42
#Sta/Elev= 30
  4277.1 1459.40  4397.1 1458.97  4428.4 1459.26  4513.4 1458.16  4647.1 1455.52
  4652.8 1455.05  4678.3 1455.01  4730.4 1453.26  4772.0 1452.44  4886.6 1448.44
  4903.1 1447.35  4917.8 1447.07  4949.1 1444.99  4969.9 1444.51  4988.6 1442.69
  4988.9 1442.19  4992.6 1442.19  4992.9 1442.69  5011.3 1444.06  5072.1 1445.57
  5143.7 1449.44  5224.2 1453.10  5274.9 1454.92  5457.5 1458.74  5501.5 1458.78
  5609.6 1457.18  5650.2 1456.20  5670.5 1455.10  5743.4 1453.58  5873.6 1449.96
#Mann=3,-1,0
  4277.1    0.05       0  4988.6    0.03       0  4992.9    0.05       0
Bank Sta=4988.6,4992.9
Exp/Cntr=0.3,0.1

Type RM Length L Ch R = 1,30000,500,500,500
BEGIN DESCRIPTION:
COTTONWOOD CREEK 60.0
END DESCRIPTION:
XS GIS Cut Line= 3
      2756218.14     10176593.91      2756485.05     10177302.83
      2756738.98     10177996.73
#Sta/Elev= 30
  4242.5 1452.91  4327.1 1450.58  4388.8 1449.84  4412.6 1450.62  4419.0 1449.65
  4424.3 1450.16  4474.1 1447.63  4487.4 1447.81  4504.3 1451.34  4529.2 1448.47
  4820.7 1445.28  4845.5 1444.00  4936.2 1441.95  4995.3 1439.04  4995.6 1438.54
  4999.6 1439.04  5010.9 1439.81  5021.7 1441.77  5102.6 1448.14  5249.9 1452.01
  5341.4 1453.32  5422.3 1453.23  5427.7 1453.80  5539.1 1451.02  5569.6 1451.10
  5649.9 1448.22  5671.2 1449.68  5686.4 1449.04  5692.5 1447.73  5738.9 1446.88
#Mann=3,-1,0
  4242.5    0.05       0  4995.3    0.05       0  4999.6    0.05       0
Bank Sta=4995.3,4999.6
Exp/Cntr=0.3,0.1

Type RM Length L Ch R = 1,29500,500,500,500
BEGIN DESCRIPTION:
COTTONWOOD CREEK 59.0
END DESCRIPTION:
XS GIS Cut Line= 3
      2755738.98     10176816.16      2756012.18     10177440.61
      2756453.59     10178079.08
#Sta/Elev= 30
  4318.4 1455.09  4413.3 1454.67  4525.1 1451.85  4571.9 1451.57  4577.3 1450.69
  4600.7 1449.86  4653.4 1449.44  4793.3 1446.30  4828.1 1445.26  4892.3 1441.03
  4897.8 1440.08  4921.1 1440.38  4926.6 1439.54  4950.0 1438.77  4967.9 1438.86
  4997.8 1434.89  4998.1 1434.39  5002.3 1434.89  5018.1 1437.35  5047.9 1437.73
  5089.8 1439.59  5379.0 1441.92  5564.2 1447.44  5594.0 1447.15  5614.9 1449.50
  5629.8 1448.50  5695.3 1449.28  5758.2 1448.87  5767.0 1448.16  5776.2 1448.65
#Mann=3,-1,0
  4318.4    0.05       0  4997.8    0.05       0  5002.3    0.05       0
Bank Sta=4997.8,5002.3
Exp/Cntr=0.3,0.1

Type RM Length L Ch R = 1,29000,500,500,500
BEGIN DESCRIPTION:
COTTONWOOD CREEK 58.0
END DESCRIPTION:
XS GIS Cut Line= 3
      2755216.86     10177155.23      2755839.64     10177898.77
      2756252.86     10178350.88
#Sta/Elev= 30
  4030.1 1447.80  4133.9 1445.34  4418.7 1444.70  4588.2 1441.53  4653.0 1441.32
  4702.4 1440.17  4716.7 1440.76  4731.0 1439.90  4815.6 1439.26  4872.9 1437.51
  4893.7 1436.14  4914.5 1436.46  4922.3 1435.59  4979.6 1433.67  4997.3 1431.72
  4997.6 1431.22  5001.8 1431.72  5007.1 1432.70  5021.3 1432.81  5049.7 1435.50
  5092.2 1436.75  5099.6 1436.02  5134.8 1438.86  5212.5 1441.34  5248.2 1441.66
  5269.2 1442.54  5290.4 1444.39  5382.7 1447.22  5502.9 1449.85  5612.5 1450.06
#Mann=3,-1,0
  4030.1    0.05       0  4997.3    0.03       0  5001.8    0.05       0
Bank Sta=4997.3,5001.8
Exp/Cntr=0.3,0.1

Type RM Length L Ch R = 1,28500,500,500,500
BEGIN DESCRIPTION:
COTTONWOOD CREEK 57.0
END DESCRIPTION:
XS GIS Cut Line= 3
      2755100.11     10177274.54      2755460.90     10178181.83
      2756070.69     10178365.68
#Sta/Elev= 30
  4023.6 1447.51  4128.9 1444.88  4404.1 1441.78  4517.4 1438.03  4541.7 1439.38
  4595.6 1439.83  4667.8 1438.78  4703.6 1437.09  4721.6 1438.02  4757.5 1437.80
  4781.8 1436.08  4811.5 1435.45  4850.7 1432.49  4865.5 1433.07  4883.0 1431.87
  4949.1 1431.55  4977.6 1429.87  4977.9 1429.37  4982.2 1429.87  5054.2 1431.08
  5059.4 1431.99  5119.9 1433.53  5203.4 1437.66  5224.3 1437.12  5267.8 1440.13
  5276.6 1439.10  5300.8 1441.56  5391.4 1445.65  5613.3 1450.21  5636.9 1449.94
#Mann=3,-1,0
  4023.6    0.05       0  4977.6    0.03       0  4982.2    0.05       0
Bank Sta=4977.6,4982.2
Exp/Cntr=0.3,0.1

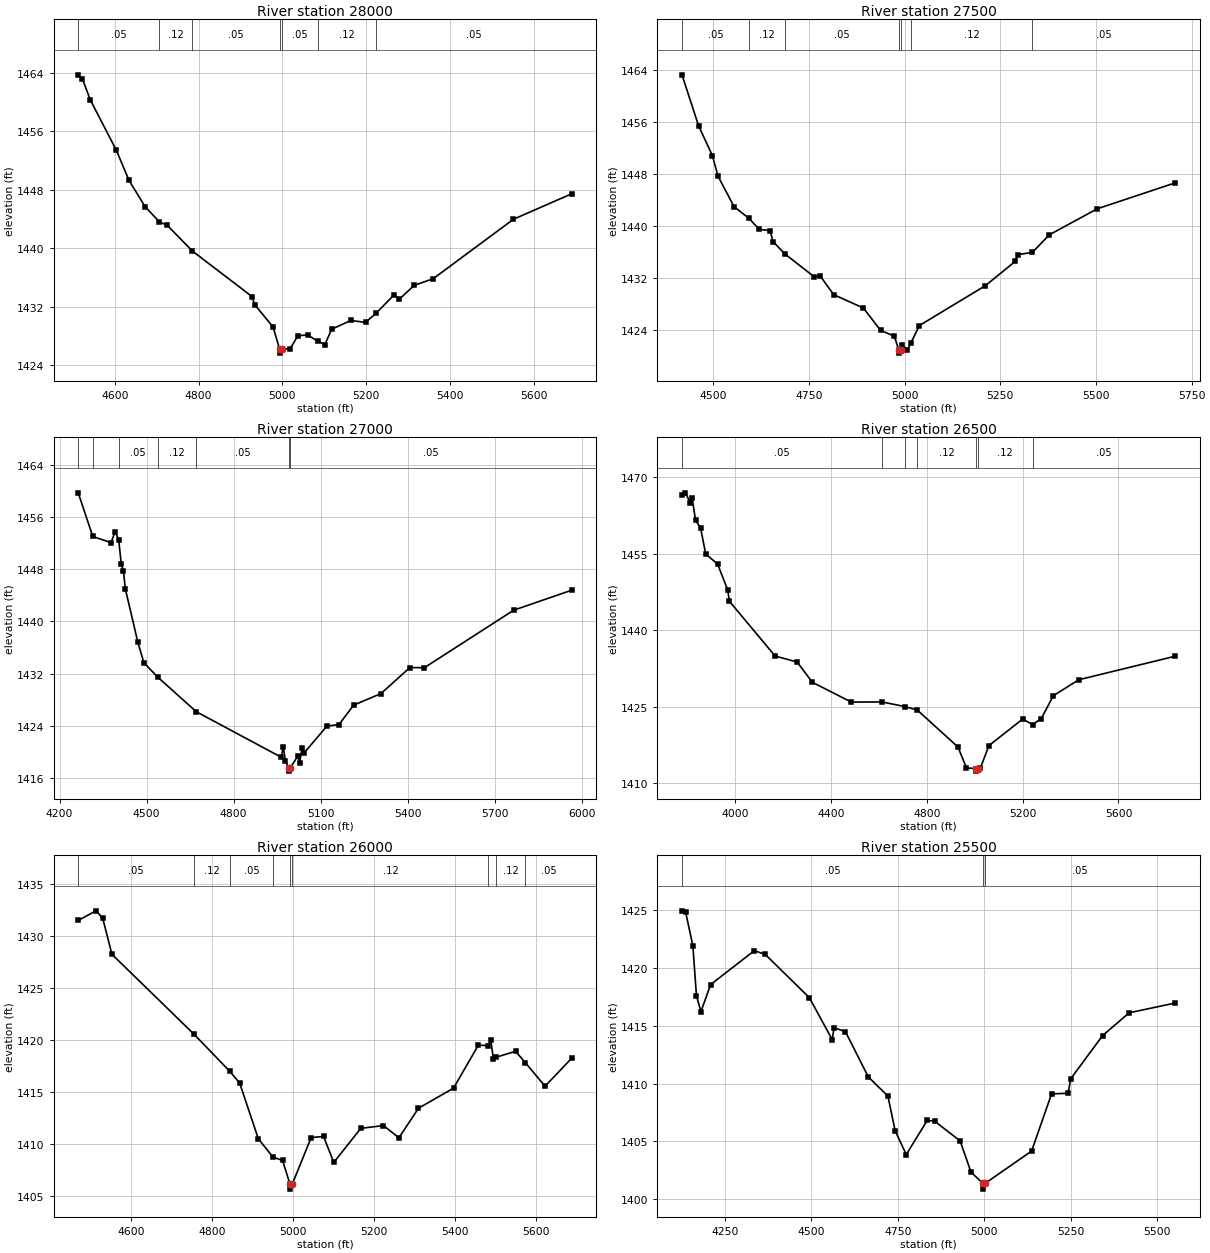
Type RM Length L Ch R = 1,28000,500,500,500
BEGIN DESCRIPTION:
COTTONWOOD CREEK 56.0
END DESCRIPTION:
XS GIS Cut Line= 3
      2754655.72     10178303.12      2755137.33     10178378.00
      2755805.67     10178553.11
#Sta/Elev= 30
  4512.6 1463.72  4522.7 1463.15  4541.5 1460.29  4603.6 1453.40  4634.0 1449.26
  4672.4 1445.67  4706.6 1443.58  4725.1 1443.13  4785.0 1439.61  4927.5 1433.37
  4934.1 1432.25  4978.1 1429.19  4993.7 1426.12  4994.2 1425.62  4999.6 1426.12
  5019.0 1426.24  5037.2 1428.00  5060.3 1428.11  5084.1 1427.27  5101.7 1426.80
  5118.0 1428.90  5163.7 1430.09  5198.8 1429.83  5223.5 1431.06  5267.1 1433.60
  5279.6 1433.01  5314.8 1434.89  5360.4 1435.81  5552.1 1443.95  5690.9 1447.43
#Mann=7,-1,0
  4512.6    0.05       0  4706.6    0.12       0  4785.0    0.05       0
  4993.7    0.05       0  4999.6    0.05       0  5084.1    0.12       0
  5223.5    0.05       0
Bank Sta=4993.7,4999.6
Exp/Cntr=0.3,0.1

Type RM Length L Ch R = 1,27500,500,500,500
BEGIN DESCRIPTION:
COTTONWOOD CREEK 55.0
END DESCRIPTION:
XS GIS Cut Line= 3
      2754605.66     10178503.10      2755085.79     10178831.15
      2755755.65     10178603.12
#Sta/Elev= 30
  4418.5 1463.21  4461.9 1455.36  4497.8 1450.81  4512.7 1447.62  4554.6 1442.94
  4593.6 1441.14  4620.4 1439.45  4648.6 1439.28  4656.3 1437.58  4686.8 1435.71
  4763.9 1432.17  4778.9 1432.34  4814.8 1429.43  4892.6 1427.36  4937.3 1423.93
  4973.2 1423.05  4984.8 1420.94  4985.3 1420.44  4990.7 1420.94  4994.2 1421.62
  5007.3 1420.95  5016.5 1422.01  5038.7 1424.68  5211.2 1430.81  5289.5 1434.56
  5295.7 1435.57  5334.1 1435.93  5378.3 1438.63  5503.8 1442.63  5707.6 1446.62
#Mann=7,-1,0
  4418.5    0.05       0  4593.6    0.12       0  4686.8    0.05       0
  4984.8    0.05       0  4990.7    0.05       0  5016.5    0.12       0
  5334.1    0.05       0
Bank Sta=4984.8,4990.7
Exp/Cntr=0.3,0.1

Type RM Length L Ch R = 1,27000,500,500,500
BEGIN DESCRIPTION:
COTTONWOOD CREEK 54.0
END DESCRIPTION:
XS GIS Cut Line= 3
      2754505.67     10178803.10      2755026.00     10179322.92
      2755805.68     10178753.11
#Sta/Elev= 30
  4264.5 1459.72  4314.8 1453.03  4377.6 1452.08  4391.8 1453.78  4404.1 1452.55
  4413.0 1448.75  4420.1 1447.79  4427.2 1444.96  4469.6 1436.91  4490.8 1433.69
  4537.9 1431.50  4671.6 1426.17  4964.6 1419.19  4971.6 1420.79  4978.7 1418.65
  4989.9 1417.56  4990.3 1417.06  4995.8 1417.56  5021.6 1419.37  5027.8 1418.33
  5036.3 1420.59  5042.5 1419.80  5122.0 1423.96  5163.7 1424.20  5213.9 1427.17
  5308.1 1428.94  5408.3 1432.94  5457.9 1432.91  5766.1 1441.73  5965.7 1444.79
#Mann=7,-1,0
  4264.5    0.05       0  4314.8    0.12       0  4404.1    0.05       0
  4537.9    0.12       0  4671.6    0.05       0  4989.9    0.05       0
  4995.8    0.05       0
Bank Sta=4989.9,4995.8
Exp/Cntr=0.3,0.1

Type RM Length L Ch R = 1,26500,500,500,500
BEGIN DESCRIPTION:
COTTONWOOD CREEK 53.0
END DESCRIPTION:
XS GIS Cut Line= 3
      2754205.70     10178953.12      2755079.18     10179809.13
      2755705.72     10179253.08
#Sta/Elev= 30
  3777.0 1466.57  3791.1 1466.99  3812.3 1465.01  3819.3 1465.98  3833.5 1461.61
  3854.8 1460.05  3875.9 1454.98  3925.5 1453.03  3967.9 1447.93  3974.9 1445.71
  4166.0 1434.96  4257.8 1433.79  4321.5 1429.81  4484.1 1425.93  4612.6 1425.95
  4707.2 1425.06  4759.5 1424.37  4929.6 1417.11  4965.0 1413.01  5005.7 1412.88
  5006.2 1412.38  5011.7 1412.88  5022.7 1412.91  5058.6 1417.37  5200.0 1422.61
  5241.2 1421.50  5277.7 1422.70  5327.9 1427.18  5434.1 1430.31  5837.7 1434.94
#Mann=7,-1,0
  3777.0    0.05       0  4612.6    0.12       0  4707.2    0.05       0
  4759.5    0.12       0  5005.7    0.07       0  5011.7    0.12       0
  5241.2    0.05       0
Bank Sta=5005.7,5011.7
Exp/Cntr=0.3,0.1

Type RM Length L Ch R = 1,26000,500,500,500
BEGIN DESCRIPTION:
COTTONWOOD CREEK 52.0
END DESCRIPTION:
XS GIS Cut Line= 3
      2754405.68     10180003.11      2754889.43     10180223.52
      2755537.58     10179989.79
#Sta/Elev= 30
  4468.4 1431.46  4512.4 1432.38  4528.8 1431.70  4551.8 1428.21  4754.6 1420.55
  4843.7 1416.97  4867.9 1415.85  4914.0 1410.51  4950.1 1408.76  4973.9 1408.43
  4992.2 1406.18  4992.7 1405.68  4998.2 1406.18  5044.6 1410.62  5075.3 1410.74
  5100.7 1408.24  5167.4 1411.51  5223.4 1411.78  5261.8 1410.61  5310.2 1413.44
  5396.9 1415.37  5458.3 1419.49  5483.1 1419.45  5489.0 1419.95  5495.6 1418.17
  5501.0 1418.32  5550.3 1418.90  5574.7 1417.81  5623.2 1415.55  5689.0 1418.23
#Mann=9,-1,0
  4468.4    0.05       0  4754.6    0.12       0  4843.7    0.05       0
  4950.1    0.12       0  4992.2    0.07       0  4998.2    0.12       0
  5483.1    0.05       0  5501.0    0.12       0  5574.7    0.05       0
Bank Sta=4992.2,4998.2
Exp/Cntr=0.3,0.1

Type RM Length L Ch R = 1,25500,500,500,500
BEGIN DESCRIPTION:
COTTONWOOD CREEK 51.0
END DESCRIPTION:
XS GIS Cut Line= 3
      2754305.65     10180253.10      2755142.69     10180504.24
      2755680.83     10180628.07
#Sta/Elev= 30
  4126.1 1424.94  4136.6 1424.83  4157.5 1421.91  4167.9 1417.58  4180.9 1416.23
  4208.8 1418.56  4334.9 1421.49  4366.3 1421.18  4494.1 1417.43  4560.3 1413.80
  4565.5 1414.83  4598.5 1414.49  4664.7 1410.57  4721.2 1408.92  4742.1 1405.92
  4774.3 1403.86  4835.2 1406.83  4857.0 1406.73  4930.0 1405.04  4961.4 1402.34
  4995.7 1401.37  4996.2 1400.87  5002.3 1401.37  5136.5 1404.16  5194.3 1409.11
  5242.2 1409.16  5249.3 1410.40  5341.7 1414.15  5418.6 1416.12  5552.2 1416.97
#Mann=3,-1,0
  4126.1    0.05       0  4995.7    0.05       0  5002.3    0.05       0
Bank Sta=4995.7,5002.3
Exp/Cntr=0.3,0.1

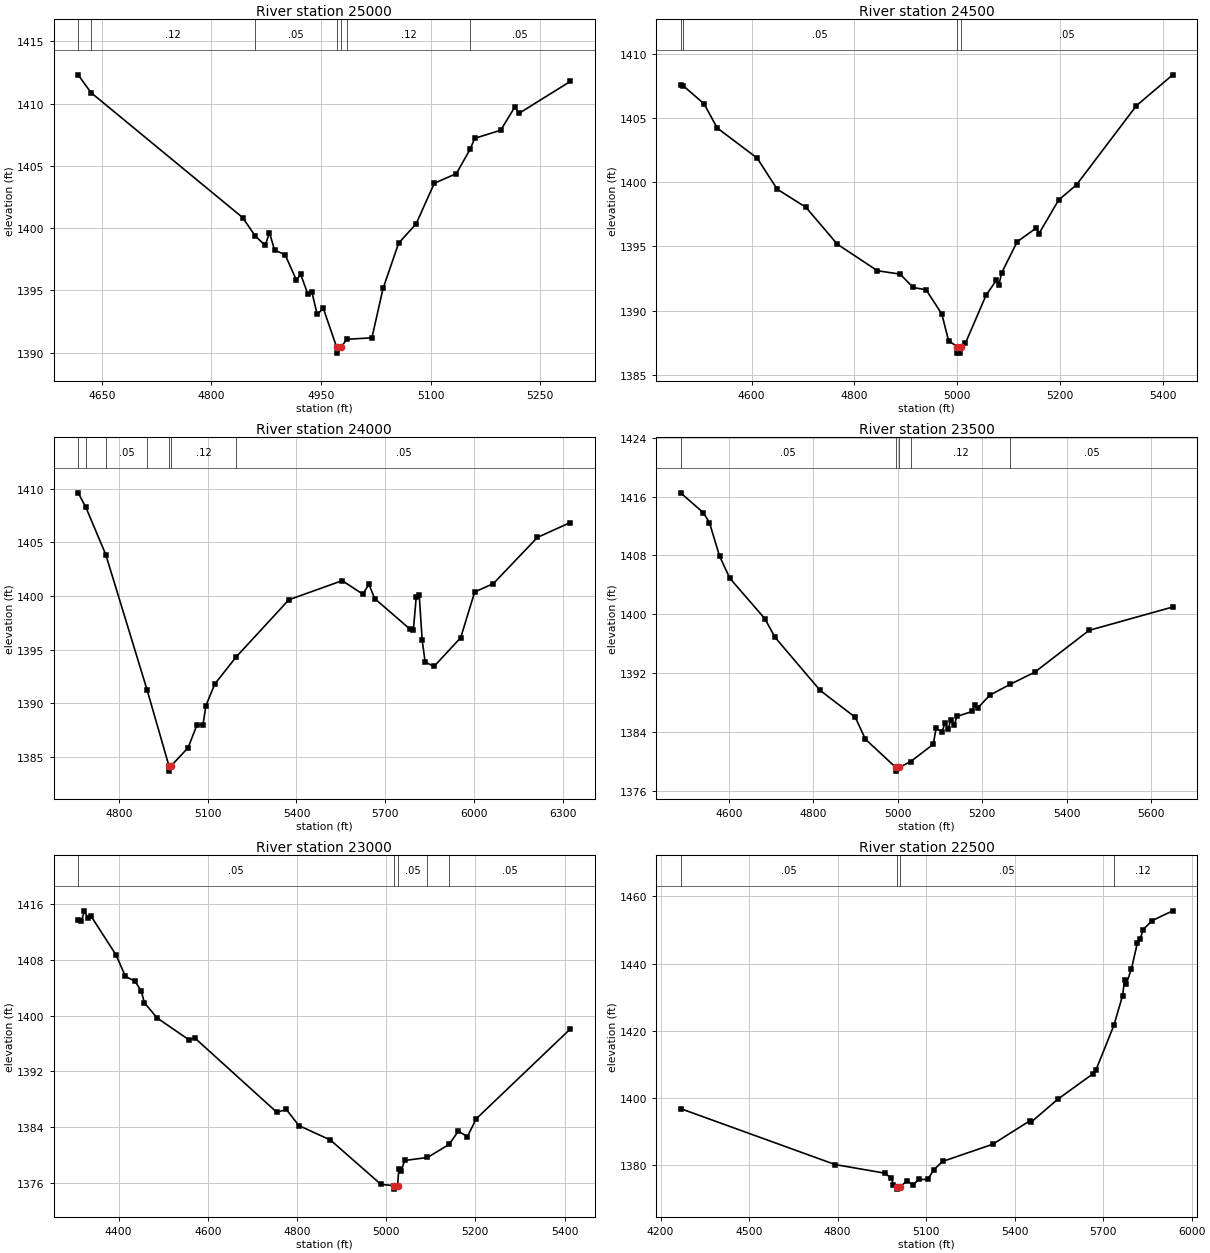
Type RM Length L Ch R = 1,25000,500,500,500
BEGIN DESCRIPTION:
COTTONWOOD CREEK 50.0
END DESCRIPTION:
XS GIS Cut Line= 3
      2754705.69     10180753.12      2755032.93     10180950.97
      2755305.73     10181053.13
#Sta/Elev= 30
  4617.6 1412.32  4635.2 1410.89  4842.7 1400.86  4860.2 1399.36  4873.7 1398.62
  4879.5 1399.65  4886.4 1398.25  4900.9 1397.87  4916.4 1395.83  4922.2 1396.30
  4931.9 1394.73  4937.7 1394.84  4944.8 1393.08  4953.2 1393.57  4971.3 1390.47
  4971.8 1389.97  4977.9 1390.47  4985.2 1391.08  5019.7 1391.20  5035.0 1395.17
  5056.3 1398.80  5080.2 1400.35  5105.1 1403.61  5135.4 1404.39  5154.2 1406.35
  5160.4 1407.22  5196.0 1407.87  5215.6 1409.76  5220.9 1409.22  5291.3 1411.79
#Mann=7,-1,0
  4617.6    0.05       0  4635.2    0.12       0  4860.2    0.05       0
  4971.3    0.07       0  4977.9    0.05       0  4985.2    0.12       0
  5154.2    0.05       0
Bank Sta=4971.3,4977.9
Exp/Cntr=0.3,0.1

Type RM Length L Ch R = 1,24500,500,500,500
BEGIN DESCRIPTION:
COTTONWOOD CREEK 49.0
END DESCRIPTION:
XS GIS Cut Line= 3
      2754655.70     10180903.16      2754839.95     10181408.94
      2755255.72     10181353.11
#Sta/Elev= 30
  4461.7 1407.54  4466.5 1407.52  4507.5 1406.10  4532.8 1404.23  4610.7 1401.88
  4649.7 1399.46  4705.6 1398.05  4766.7 1395.18  4844.8 1393.11  4889.0 1392.85
  4914.2 1391.81  4939.5 1391.63  4970.1 1389.74  4983.2 1387.67  5000.1 1387.20
  5000.6 1386.70  5006.3 1386.70  5006.8 1387.20  5015.9 1387.46  5056.2 1391.21
  5076.4 1392.38  5081.4 1392.04  5086.5 1392.95  5116.8 1395.37  5154.3 1396.45
  5159.3 1396.01  5197.5 1398.62  5232.2 1399.80  5348.8 1405.96  5419.5 1408.36
#Mann=4,-1,0
  4461.7    0.12       0  4466.5    0.05       0  5000.1    0.05       0
  5006.8    0.05       0
Bank Sta=5000.1,5006.8
Exp/Cntr=0.3,0.1

Type RM Length L Ch R = 1,24000,500,500,500
BEGIN DESCRIPTION:
COTTONWOOD CREEK 48.0
END DESCRIPTION:
XS GIS Cut Line= 3
      2754255.70     10181803.11      2754581.82     10181715.05
      2755905.67     10181653.11
#Sta/Elev= 30
  4662.2 1409.60  4688.4 1408.24  4755.5 1403.85  4895.4 1391.22  4968.9 1384.18
  4969.4 1383.68  4977.0 1384.18  5033.9 1385.87  5063.9 1388.00  5084.0 1387.99
  5094.0 1389.78  5124.0 1391.80  5197.0 1394.34  5374.3 1399.64  5554.5 1401.42
  5624.5 1400.16  5644.6 1401.08  5664.6 1399.74  5784.7 1396.88  5795.1 1396.87
  5804.7 1399.91  5814.8 1400.06  5824.8 1395.85  5834.8 1393.84  5864.8 1393.43
  5954.9 1396.11  6002.2 1400.37  6065.0 1401.14  6214.3 1405.45  6325.3 1406.83
#Mann=7,-1,0
  4662.2    0.05       0  4688.4    0.12       0  4755.5    0.05       0
  4895.4    0.12       0  4968.9    0.07       0  4977.0    0.12       0
  5197.0    0.05       0
Bank Sta=4968.9,4977
Exp/Cntr=0.3,0.1

Type RM Length L Ch R = 1,23500,500,500,500
BEGIN DESCRIPTION:
COTTONWOOD CREEK 47.0
END DESCRIPTION:
XS GIS Cut Line= 3
      2754205.67     10182003.10      2754681.73     10182196.91
      2755105.66     10181703.13
#Sta/Elev= 30
  4486.0 1416.53  4540.0 1413.82  4554.3 1412.47  4578.3 1407.91  4602.4 1404.91
  4685.3 1399.41  4709.4 1396.87  4816.4 1389.63  4899.4 1385.98  4923.5 1382.99
  4995.4 1379.15  4995.9 1378.65  5003.5 1379.15  5030.3 1379.94  5084.0 1382.31
  5090.6 1384.46  5104.9 1384.02  5111.5 1385.20  5119.1 1384.36  5125.7 1385.66
  5133.4 1384.87  5140.0 1386.10  5176.2 1386.77  5182.8 1387.68  5189.5 1387.26
  5217.9 1388.99  5266.6 1390.48  5324.3 1392.12  5452.7 1397.81  5650.8 1400.99
#Mann=5,-1,0
  4486.0    0.05       0  4995.4    0.05       0  5003.5    0.05       0
  5030.3    0.12       0  5266.6    0.05       0
Bank Sta=4995.4,5003.5
Exp/Cntr=0.3,0.1

Type RM Length L Ch R = 1,23000,500,500,500
BEGIN DESCRIPTION:
COTTONWOOD CREEK 46.0
END DESCRIPTION:
XS GIS Cut Line= 3
      2754205.68     10182203.11      2754694.39     10182690.90
      2755105.66     10182653.11
#Sta/Elev= 30
  4309.5 1413.72  4316.6 1413.58  4323.6 1415.08  4330.7 1414.11  4337.8 1414.38
  4394.4 1408.74  4415.6 1405.64  4436.8 1404.96  4450.9 1403.55  4458.0 1401.87
  4486.3 1399.68  4557.0 1396.57  4571.1 1396.79  4755.0 1386.10  4776.2 1386.51
  4804.5 1384.19  4875.2 1382.11  4988.3 1375.74  5017.1 1375.55  5017.6 1375.05
  5025.7 1375.55  5028.5 1377.90  5033.5 1377.60  5041.5 1379.17  5092.7 1379.60
  5141.2 1381.48  5162.0 1383.39  5182.1 1382.60  5202.1 1385.17  5413.0 1398.09
#Mann=5,-1,0
  4309.5    0.05       0  5017.1    0.05       0  5025.7    0.05       0
  5092.7    0.12       0  5141.2    0.05       0
Bank Sta=5017.1,5025.7
Exp/Cntr=0.3,0.1

Type RM Length L Ch R = 1,22500,500,500,500
BEGIN DESCRIPTION:
COTTONWOOD CREEK 45.0
END DESCRIPTION:
XS GIS Cut Line= 3
      2754055.65     10182653.08      2754570.26     10183174.08
      2755505.71     10183203.11
#Sta/Elev= 30
  4267.7 1396.83  4791.0 1380.19  4960.7 1377.60  4982.0 1376.04  4989.0 1374.19
  5001.1 1373.36  5001.6 1372.86  5009.8 1373.36  5035.4 1375.37  5055.4 1374.10
  5075.5 1375.76  5105.5 1375.73  5125.2 1378.55  5155.5 1381.09  5325.6 1386.22
  5451.5 1393.20  5456.5 1392.85  5545.7 1399.58  5665.7 1407.21  5675.7 1408.35
  5736.2 1421.58  5765.8 1430.45  5772.7 1435.23  5777.7 1433.82  5795.8 1438.39
  5815.8 1446.08  5825.8 1447.38  5835.8 1450.14  5865.8 1452.79  5935.9 1455.71
#Mann=4,-1,0
  4267.7    0.05       0  5001.1    0.03       0  5009.8    0.05       0
  5736.2    0.12       0
Bank Sta=5001.1,5009.8
Exp/Cntr=0.3,0.1

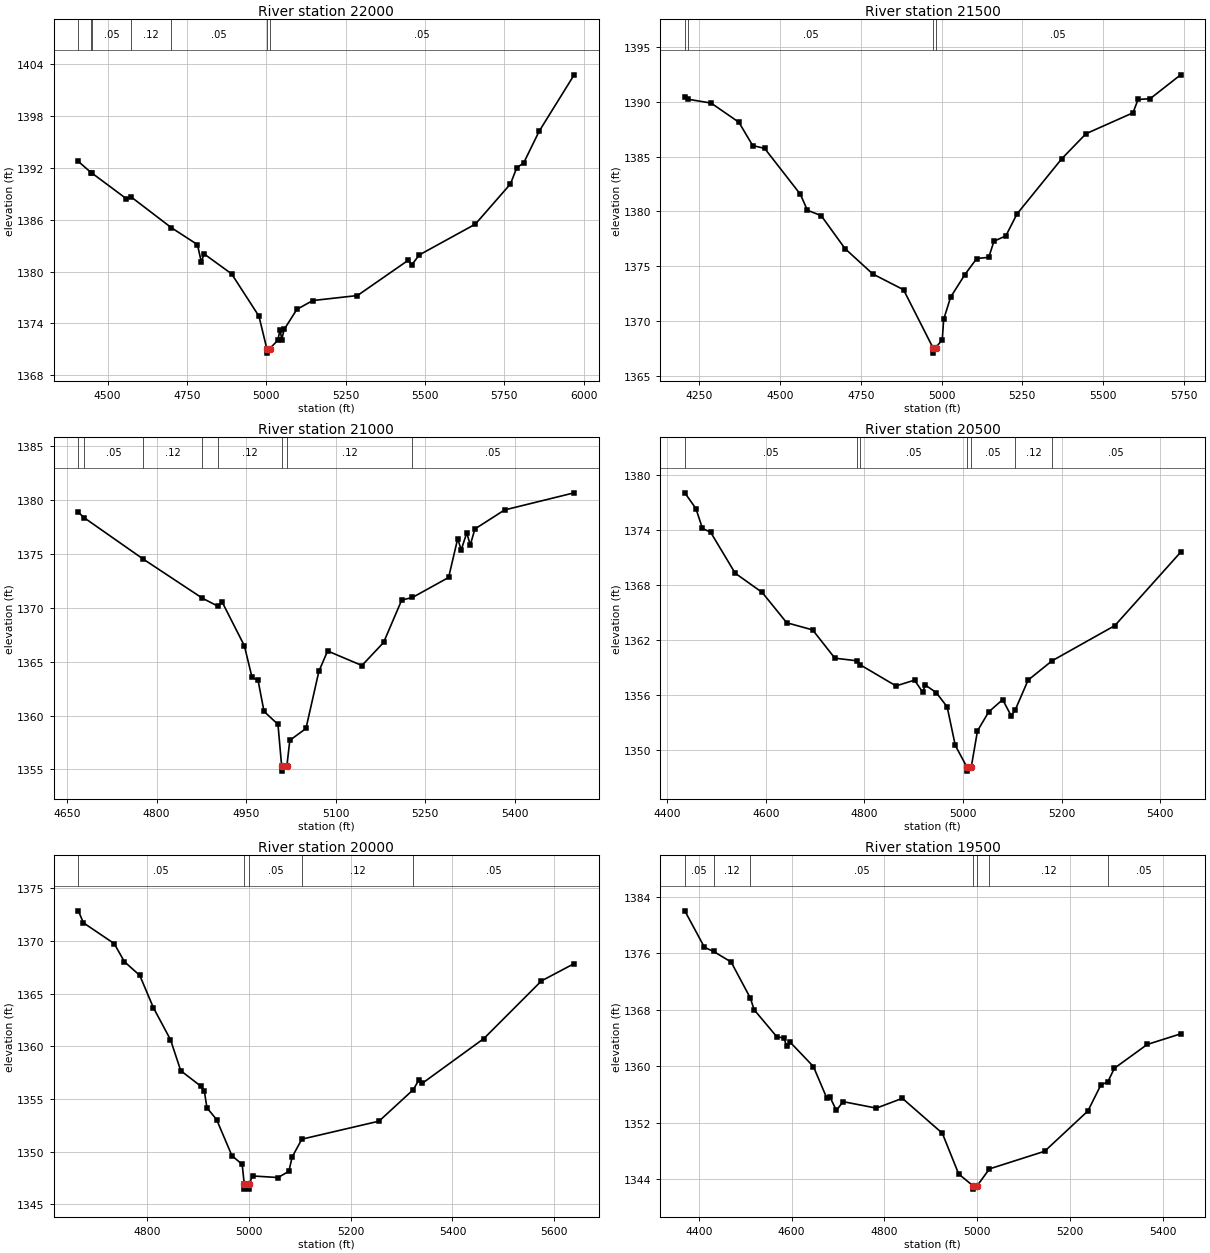
Type RM Length L Ch R = 1,22000,500,500,500
BEGIN DESCRIPTION:
COTTONWOOD CREEK 44.0
END DESCRIPTION:
XS GIS Cut Line= 3
      2753905.68     10183003.11      2754239.76     10183492.33
      2755205.65     10183403.12
#Sta/Elev= 30
  4407.6 1392.76  4448.9 1391.43  4451.9 1391.37  4558.6 1388.45  4573.1 1388.67
  4701.0 1385.08  4782.9 1383.13  4795.1 1381.12  4803.9 1382.05  4890.6 1379.74
  4976.7 1374.84  5001.6 1371.06  5002.1 1370.56  5010.3 1371.06  5036.1 1372.05
  5043.5 1373.28  5048.5 1372.13  5056.2 1373.30  5096.3 1375.63  5146.5 1376.65
  5287.1 1377.23  5447.8 1381.33  5457.9 1380.76  5481.9 1381.93  5658.7 1385.50
  5769.2 1390.15  5789.3 1392.04  5810.7 1392.57  5859.6 1396.25  5970.0 1402.79
#Mann=7,-1,0
  4407.6    0.05       0  4448.9    0.12       0  4451.9    0.05       0
  4573.1    0.12       0  4701.0    0.05       0  5001.6    0.05       0
  5010.3    0.05       0
Bank Sta=5001.6,5010.3
Exp/Cntr=0.3,0.1

Type RM Length L Ch R = 1,21500,500,500,500
BEGIN DESCRIPTION:
COTTONWOOD CREEK 43.0
END DESCRIPTION:
XS GIS Cut Line= 3
      2753705.71     10183253.15      2754112.92     10183936.05
      2754755.69     10184303.12
#Sta/Elev= 30
  4204.9 1390.41  4214.8 1390.25  4286.4 1389.90  4372.3 1388.15  4415.1 1386.02
  4452.1 1385.76  4563.0 1381.56  4584.4 1380.11  4627.2 1379.62  4701.2 1376.60
  4787.0 1374.29  4882.2 1372.85  4973.2 1367.56  4973.7 1367.06  4982.0 1367.56
  5002.1 1368.29  5006.5 1370.14  5028.1 1372.18  5072.3 1374.24  5108.8 1375.70
  5146.2 1375.81  5162.1 1377.28  5199.0 1377.77  5233.5 1379.77  5372.3 1384.82
  5447.2 1387.10  5592.6 1389.01  5608.4 1390.23  5645.9 1390.30  5740.2 1392.48
#Mann=4,-1,0
  4204.9    0.12       0  4214.8    0.05       0  4973.2    0.05       0
  4982.0    0.05       0
Bank Sta=4973.2,4982
Exp/Cntr=0.3,0.1

Type RM Length L Ch R = 1,21000,500,500,500
BEGIN DESCRIPTION:
COTTONWOOD CREEK 42.0
END DESCRIPTION:
XS GIS Cut Line= 3
      2753655.69     10183803.12      2753685.20     10184133.11
      2754105.68     10184403.11
#Sta/Elev= 30
  4668.7 1378.88  4678.6 1378.37  4777.6 1374.53  4876.7 1370.90  4903.3 1370.14
  4909.6 1370.56  4947.0 1366.48  4959.8 1363.55  4969.9 1363.28  4979.9 1360.39
  5003.3 1359.18  5009.4 1355.34  5009.9 1354.84  5018.3 1355.34  5023.1 1357.70
  5050.2 1358.80  5071.9 1364.12  5086.5 1366.00  5144.0 1364.65  5180.3 1366.79
  5210.7 1370.73  5228.7 1370.97  5289.3 1372.83  5304.5 1376.43  5310.4 1375.39
  5319.7 1376.97  5325.6 1375.84  5333.3 1377.33  5383.1 1379.10  5499.7 1380.69
#Mann=8,-1,0
  4668.7    0.12       0  4678.6    0.05       0  4777.6    0.12       0
  4876.7    0.05       0  4903.3    0.12       0  5009.4    0.07       0
  5018.3    0.12       0  5228.7    0.05       0
Bank Sta=5009.4,5018.3
Exp/Cntr=0.3,0.1

Type RM Length L Ch R = 1,20500,500,500,500
BEGIN DESCRIPTION:
COTTONWOOD CREEK 41.0
END DESCRIPTION:
XS GIS Cut Line= 3
      2753055.71     10184853.10      2753556.25     10184591.66
      2753955.68     10184403.11
#Sta/Elev= 30
  4435.3 1378.03  4457.8 1376.32  4471.2 1374.15  4487.7 1373.74  4537.5 1369.28
  4592.4 1367.18  4642.2 1363.88  4694.8 1363.10  4739.9 1360.02  4784.3 1359.74
  4791.6 1359.29  4864.0 1357.00  4901.6 1357.63  4918.0 1356.33  4923.6 1357.09
  4945.7 1356.27  4967.8 1354.72  4984.3 1350.52  5007.3 1348.22  5007.8 1347.72
  5016.9 1348.22  5029.4 1352.11  5052.2 1354.17  5080.5 1355.51  5097.7 1353.75
  5105.7 1354.35  5132.1 1357.63  5180.6 1359.73  5308.2 1363.57  5441.7 1371.56
#Mann=7,-1,0
  4435.3    0.05       0  4784.3    0.12       0  4791.6    0.05       0
  5007.3    0.05       0  5016.9    0.05       0  5105.7    0.12       0
  5180.6    0.05       0
Bank Sta=5007.3,5016.9
Exp/Cntr=0.3,0.1

Type RM Length L Ch R = 1,20000,500,500,500
BEGIN DESCRIPTION:
COTTONWOOD CREEK 40.0
END DESCRIPTION:
XS GIS Cut Line= 3
      2753205.69     10185053.11      2753538.39     10185086.76
      2753955.69     10184603.10
#Sta/Elev= 30
  4665.6 1372.85  4675.6 1371.71  4736.0 1369.74  4756.1 1368.02  4786.2 1366.72
  4813.0 1363.65  4846.5 1360.62  4866.6 1357.68  4906.8 1356.18  4913.0 1355.72
  4918.0 1354.16  4937.0 1353.04  4967.1 1349.61  4987.2 1348.79  4991.2 1346.94
  4991.7 1346.44  5000.5 1346.44  5001.0 1346.94  5007.5 1347.69  5057.6 1347.54
  5078.8 1348.13  5085.4 1349.50  5104.3 1351.18  5255.8 1352.89  5323.0 1355.88
  5334.3 1356.82  5340.9 1356.49  5461.6 1360.73  5574.6 1366.20  5638.8 1367.84
#Mann=5,-1,0
  4665.6    0.05       0  4991.2    0.05       0  5001.0    0.05       0
  5104.3    0.12       0  5323.0    0.05       0
Bank Sta=4991.2,5001
Exp/Cntr=0.3,0.1

Type RM Length L Ch R = 1,19500,500,500,500
BEGIN DESCRIPTION:
COTTONWOOD CREEK 39.0
END DESCRIPTION:
XS GIS Cut Line= 3
      2753305.65     10185903.14      2753793.43     10185504.13
      2754055.71     10185153.08
#Sta/Elev= 30
  4369.8 1382.00  4412.2 1376.83  4431.9 1376.25  4469.6 1374.76  4511.0 1369.66
  4519.2 1368.00  4568.7 1364.13  4583.0 1364.05  4589.5 1362.83  4597.4 1363.37
  4646.9 1359.97  4675.6 1355.53  4682.1 1355.71  4696.5 1353.75  4710.8 1355.00
  4782.6 1354.08  4838.6 1355.47  4924.7 1350.53  4959.9 1344.77  4990.2 1343.12
  4990.7 1342.62  5000.0 1343.12  5026.2 1345.48  5145.3 1347.98  5238.4 1353.68
  5266.2 1357.34  5281.5 1357.82  5295.4 1359.72  5366.2 1363.09  5438.2 1364.59
#Mann=7,-1,0
  4369.8    0.05       0  4431.9    0.12       0  4511.0    0.05       0
  4990.2    0.05       0  5000.0    0.05       0  5026.2    0.12       0
  5281.5    0.05       0
Bank Sta=4990.2,5000
Exp/Cntr=0.3,0.1