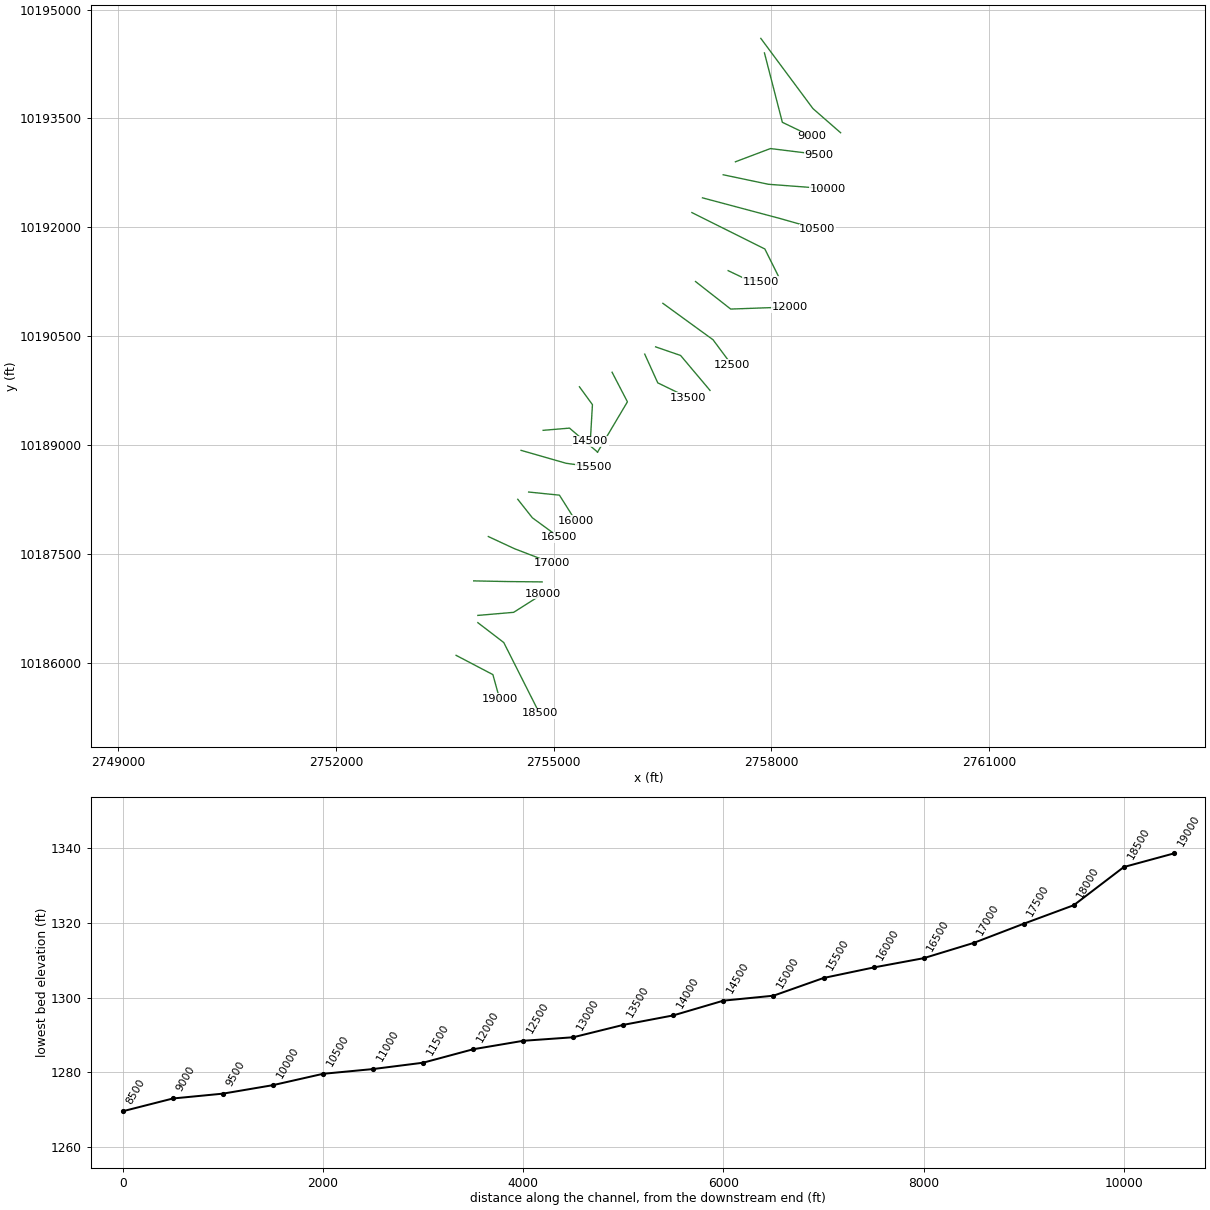
HEC-RAS study COTTONWOOD CREEK.prj: COTTONWOOD CREEK Base Level Engineering

--- COTTONWOOD CREEK.g01 (geometry) --- (continued)

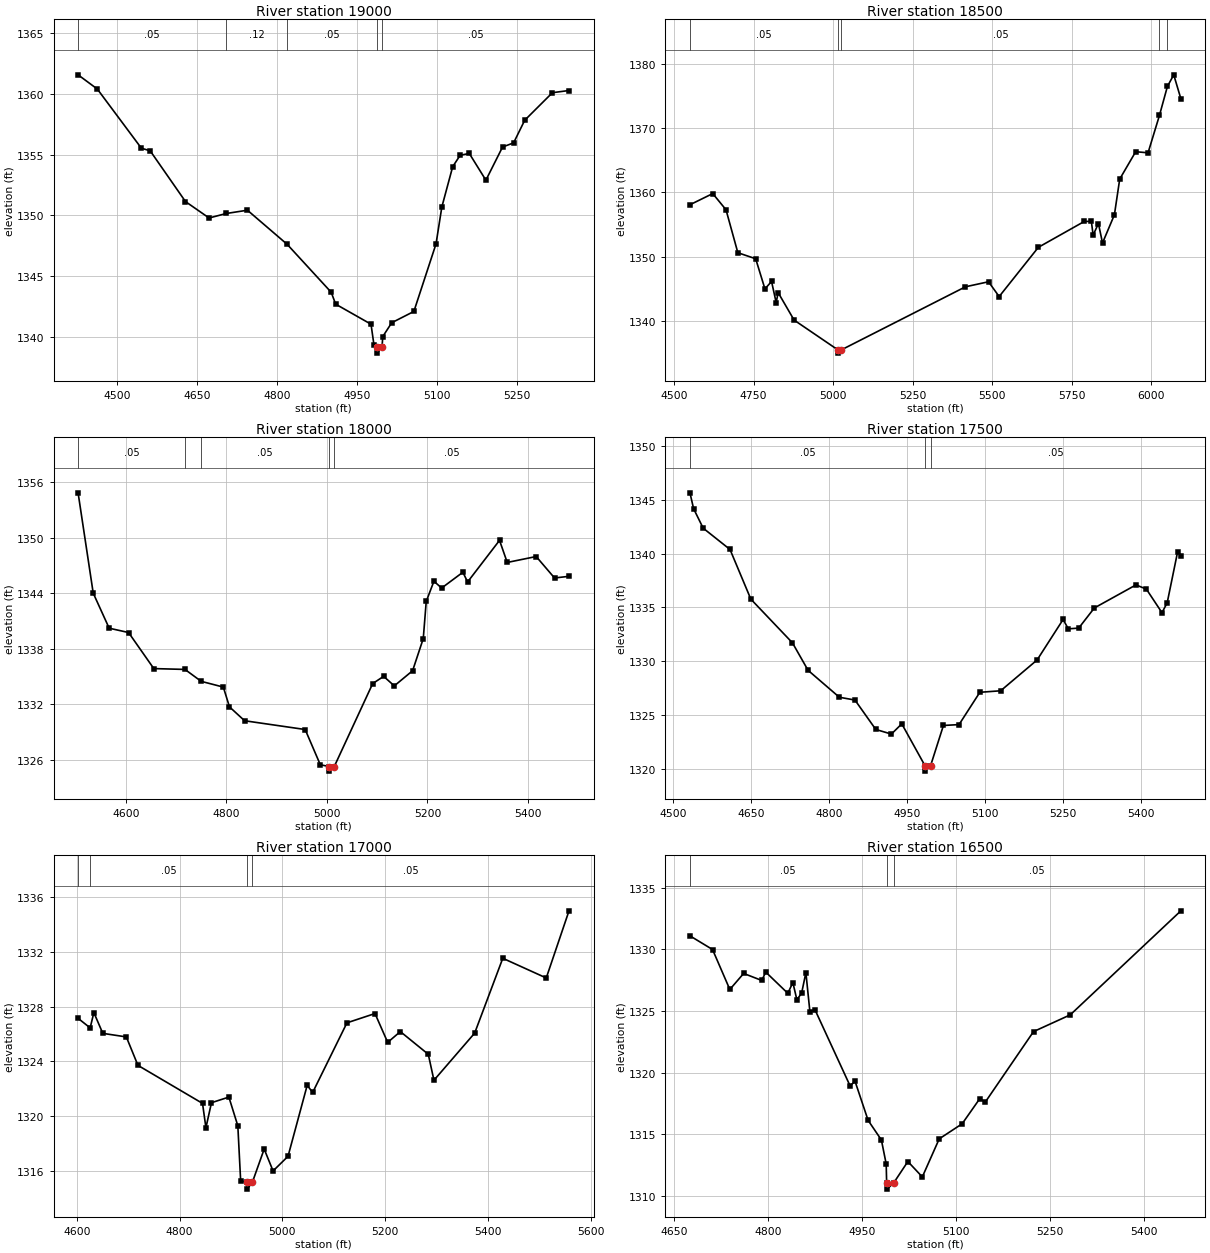
Type RM Length L Ch R = 1,19000,500,500,500
BEGIN DESCRIPTION:
COTTONWOOD CREEK 38.0
END DESCRIPTION:
XS GIS Cut Line= 3
      2753655.65     10186103.13      2754162.76     10185837.66
      2754255.68     10185503.12
#Sta/Elev= 30
  4427.6 1361.56  4463.6 1360.39  4546.2 1355.52  4562.6 1355.31  4628.8 1351.13
  4673.0 1349.78  4705.2 1350.15  4744.8 1350.42  4819.3 1347.61  4901.7 1343.67
  4910.1 1342.69  4976.3 1341.04  4981.9 1339.32  4987.1 1339.16  4987.6 1338.66
  4997.0 1339.16  4998.3 1340.02  5015.1 1341.16  5056.6 1342.09  5098.1 1347.65
  5109.0 1350.69  5129.3 1354.00  5143.3 1354.94  5160.4 1355.09  5191.5 1352.89
  5222.7 1355.62  5243.4 1355.96  5264.2 1357.82  5316.1 1360.09  5347.2 1360.27
#Mann=5,-1,0
  4427.6    0.05       0  4705.2    0.12       0  4819.3    0.05       0
  4987.1    0.05       0  4997.0    0.05       0
Bank Sta=4987.1,4997
Exp/Cntr=0.3,0.1

Type RM Length L Ch R = 1,18500,500,500,500
BEGIN DESCRIPTION:
COTTONWOOD CREEK 37.0
END DESCRIPTION:
XS GIS Cut Line= 3
      2753955.66     10186553.13      2754312.84     10186279.58
      2754805.69     10185303.10
#Sta/Elev= 30
  4550.1 1358.09  4621.8 1359.83  4663.5 1357.31  4700.7 1350.63  4756.8 1349.69
  4785.9 1345.00  4806.7 1346.16  4821.2 1342.88  4827.5 1344.42  4877.6 1340.15
  5015.5 1335.51  5016.0 1335.01  5025.9 1335.51  5416.5 1345.33  5489.0 1346.11
  5522.4 1343.81  5645.7 1351.47  5790.0 1355.49  5812.3 1355.51  5817.9 1353.37
  5834.6 1355.17  5847.4 1352.14  5884.8 1356.53  5901.5 1362.08  5951.7 1366.34
  5990.6 1366.17  6026.4 1371.98  6051.5 1376.50  6071.4 1378.30  6093.8 1374.58
#Mann=5,-1,0
  4550.1    0.05       0  5015.5    0.03       0  5025.9    0.05       0
  6026.4    0.12       0  6051.5    0.05       0
Bank Sta=5015.5,5025.9
Exp/Cntr=0.3,0.1

Type RM Length L Ch R = 1,18000,500,500,500
BEGIN DESCRIPTION:
COTTONWOOD CREEK 36.0
END DESCRIPTION:
XS GIS Cut Line= 3
      2753955.67     10186653.11      2754448.65     10186695.51
      2754855.68     10186953.11
#Sta/Elev= 30
  4505.2 1354.87  4535.3 1344.02  4567.0 1340.23  4605.6 1339.76  4655.8 1335.86
  4717.8 1335.77  4750.1 1334.48  4794.1 1333.86  4806.3 1331.72  4836.4 1330.22
  4956.9 1329.27  4987.0 1325.46  5004.3 1325.27  5004.8 1324.77  5014.8 1325.27
  5091.2 1334.24  5113.0 1335.02  5134.2 1333.99  5170.6 1335.63  5191.8 1339.11
  5197.7 1343.12  5213.0 1345.31  5228.3 1344.57  5270.6 1346.28  5280.0 1345.23
  5343.5 1349.73  5358.8 1347.34  5416.4 1347.98  5452.9 1345.66  5481.7 1345.84
#Mann=5,-1,0
  4505.2    0.05       0  4717.8    0.12       0  4750.1    0.05       0
  5004.3    0.05       0  5014.8    0.05       0
Bank Sta=5004.3,5014.8
Exp/Cntr=0.3,0.1

Type RM Length L Ch R = 1,17500,500,500,500
BEGIN DESCRIPTION:
COTTONWOOD CREEK 35.0
END DESCRIPTION:
XS GIS Cut Line= 3
      2753898.68     10187128.67      2754365.89     10187119.59
      2754841.97     10187114.79
#Sta/Elev= 30
  4532.7 1345.64  4539.7 1344.17  4558.1 1342.36  4609.7 1340.38  4649.7 1335.77
  4729.7 1331.71  4759.7 1329.16  4819.8 1326.66  4849.8 1326.40  4889.8 1323.67
  4919.8 1323.24  4939.8 1324.19  4984.4 1320.30  4984.9 1319.80  4995.1 1320.30
  5019.8 1324.04  5049.8 1324.12  5089.8 1327.12  5129.8 1327.26  5199.8 1330.12
  5249.8 1333.88  5259.8 1333.01  5279.8 1333.08  5309.8 1334.95  5389.8 1337.09
  5409.8 1336.70  5439.8 1334.51  5449.8 1335.43  5469.8 1340.15  5476.1 1339.81
#Mann=3,-1,0
  4532.7    0.05       0  4984.4    0.05       0  4995.1    0.05       0
Bank Sta=4984.4,4995.1
Exp/Cntr=0.3,0.1

Type RM Length L Ch R = 1,17000,500,500,500
BEGIN DESCRIPTION:
COTTONWOOD CREEK 34.0
END DESCRIPTION:
XS GIS Cut Line= 3
      2754100.09     10187739.78      2754460.54     10187572.20
      2754981.38     10187371.98
#Sta/Elev= 30
  4602.5 1327.14  4626.0 1326.44  4633.2 1327.56  4650.6 1326.04  4696.4 1325.78
  4719.0 1323.70  4844.7 1320.92  4851.3 1319.14  4862.1 1320.97  4896.0 1321.38
  4913.4 1319.28  4918.9 1315.26  4930.9 1315.15  4931.4 1314.65  4941.7 1315.15
  4964.7 1317.58  4982.0 1315.98  5011.1 1317.05  5048.4 1322.24  5059.1 1321.72
  5125.8 1326.81  5180.4 1327.49  5205.1 1325.38  5229.7 1326.17  5284.1 1324.51
  5295.1 1322.61  5374.4 1326.06  5429.1 1331.53  5513.7 1330.09  5558.0 1335.00
#Mann=4,-1,0
  4602.5    0.12       0  4626.0    0.05       0  4930.9    0.05       0
  4941.7    0.05       0
Bank Sta=4930.9,4941.7
Exp/Cntr=0.3,0.1

Type RM Length L Ch R = 1,16500,500,500,500
BEGIN DESCRIPTION:
COTTONWOOD CREEK 33.0
END DESCRIPTION:
XS GIS Cut Line= 3
      2754505.67     10188253.13      2754707.02     10187998.02
      2755077.72     10187727.02
#Sta/Elev= 30
  4675.0 1331.10  4711.1 1329.99  4738.7 1326.75  4760.8 1328.05  4789.7 1327.48
  4796.1 1328.16  4831.3 1326.44  4839.4 1327.31  4845.8 1325.92  4853.4 1326.45
  4860.2 1328.12  4866.6 1324.95  4874.6 1325.12  4930.7 1318.94  4938.8 1319.29
  4959.6 1316.13  4980.8 1314.54  4988.5 1312.59  4989.2 1311.05  4989.7 1310.55
  5000.4 1311.05  5023.1 1312.79  5046.2 1311.54  5073.2 1314.63  5109.8 1315.85
  5138.1 1317.90  5146.6 1317.60  5223.8 1323.33  5282.5 1324.69  5459.2 1333.13
#Mann=3,-1,0
  4675.0    0.05       0  4989.2    0.05       0  5000.4    0.05       0
Bank Sta=4989.2,5000.4
Exp/Cntr=0.3,0.1

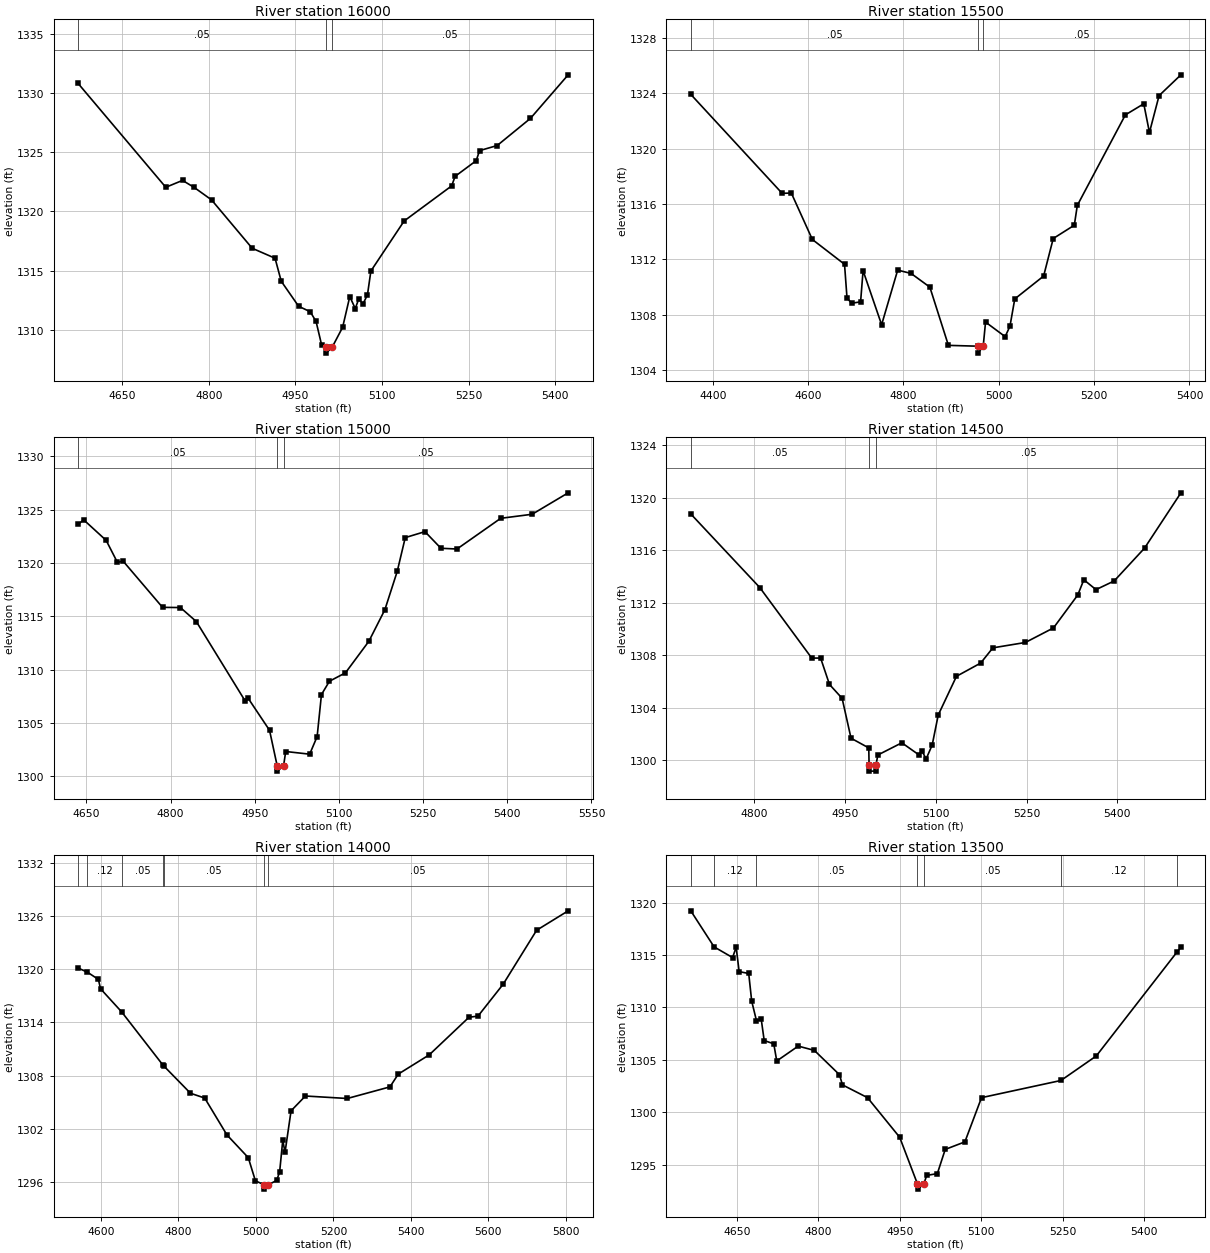
Type RM Length L Ch R = 1,16000,500,500,500
BEGIN DESCRIPTION:
COTTONWOOD CREEK 32.0
END DESCRIPTION:
XS GIS Cut Line= 3
      2754655.73     10188353.11      2755079.93     10188309.91
      2755305.67     10187953.13
#Sta/Elev= 30
  4573.6 1330.80  4725.5 1322.04  4754.5 1322.62  4774.6 1322.03  4804.7 1320.98
  4875.1 1316.90  4914.7 1316.06  4925.4 1314.12  4955.5 1312.01  4975.6 1311.55
  4985.7 1310.73  4995.4 1308.73  5002.4 1308.56  5002.9 1308.06  5013.6 1308.56
  5031.7 1310.24  5044.1 1312.83  5053.5 1311.82  5059.4 1312.59  5067.2 1312.23
  5074.7 1312.98  5080.6 1314.98  5138.2 1319.20  5220.5 1322.16  5226.4 1322.96
  5262.9 1324.28  5268.8 1325.13  5299.3 1325.56  5356.9 1327.85  5422.2 1331.52
#Mann=3,-1,0
  4573.6    0.05       0  5002.4    0.05       0  5013.6    0.05       0
Bank Sta=5002.4,5013.6
Exp/Cntr=0.3,0.1

Type RM Length L Ch R = 1,15500,500,500,500
BEGIN DESCRIPTION:
COTTONWOOD CREEK 31.0
END DESCRIPTION:
XS GIS Cut Line= 3
      2754551.47     10188927.28      2755172.50     10188749.03
      2755551.10     10188698.17
#Sta/Elev= 30
  4353.9 1323.91  4545.5 1316.77  4564.8 1316.79  4608.9 1313.44  4676.4 1311.65
  4681.6 1309.22  4691.2 1308.84  4710.1 1308.94  4715.3 1311.19  4754.2 1307.29
  4787.9 1311.23  4816.0 1310.99  4855.4 1310.00  4894.3 1305.80  4956.1 1305.74
  4956.6 1305.24  4967.3 1305.74  4972.2 1307.48  5013.3 1306.43  5023.4 1307.18
  5033.5 1309.15  5094.0 1310.80  5114.2 1313.51  5158.4 1314.47  5164.7 1315.90
  5265.5 1322.43  5304.1 1323.23  5316.0 1321.16  5336.2 1323.82  5382.0 1325.32
#Mann=3,-1,0
  4353.9    0.05       0  4956.1    0.05       0  4967.3    0.05       0
Bank Sta=4956.1,4967.3
Exp/Cntr=0.3,0.1

Type RM Length L Ch R = 1,15000,500,500,500
BEGIN DESCRIPTION:
COTTONWOOD CREEK 30.0
END DESCRIPTION:
XS GIS Cut Line= 3
      2754855.73     10189203.12      2755219.25     10189233.64
      2755605.68     10188903.12
#Sta/Elev= 30
  4635.2 1323.62  4645.2 1324.06  4685.3 1322.13  4705.4 1320.06  4715.4 1320.19
  4785.7 1315.85  4817.6 1315.83  4845.9 1314.52  4932.6 1307.10  4937.6 1307.38
  4976.4 1304.32  4990.0 1300.99  4990.5 1300.49  5001.4 1300.99  5005.2 1302.33
  5047.9 1302.08  5061.2 1303.73  5068.9 1307.67  5083.1 1308.92  5111.7 1309.71
  5153.4 1312.67  5181.9 1315.63  5203.9 1319.22  5218.2 1322.39  5253.3 1322.95
  5281.8 1321.39  5310.4 1321.32  5388.3 1324.20  5444.3 1324.58  5508.5 1326.59
#Mann=3,-1,0
  4635.2    0.05       0  4990.0    0.05       0  5001.4    0.05       0
Bank Sta=4990,5001.4
Exp/Cntr=0.3,0.1

Type RM Length L Ch R = 1,14500,500,500,500
BEGIN DESCRIPTION:
COTTONWOOD CREEK 29.0
END DESCRIPTION:
XS GIS Cut Line= 3
      2755355.69     10189803.11      2755535.03     10189557.15
      2755505.68     10189053.10
#Sta/Elev= 30
  4695.6 1318.77  4809.5 1313.16  4895.3 1307.78  4910.0 1307.78  4924.6 1305.77
  4945.5 1304.71  4960.2 1301.67  4989.5 1300.93  4990.0 1299.66  4990.5 1299.16
  5001.0 1299.16  5001.5 1299.66  5004.5 1300.39  5044.1 1301.32  5072.0 1300.41
  5077.0 1300.73  5084.2 1300.09  5094.2 1301.15  5104.2 1303.44  5134.3 1306.39
  5174.3 1307.40  5194.4 1308.56  5248.1 1308.97  5294.5 1310.08  5334.6 1312.59
  5344.6 1313.75  5364.7 1313.00  5394.7 1313.66  5444.8 1316.16  5504.9 1320.38
#Mann=3,-1,0
  4695.6    0.05       0  4990.0    0.03       0  5001.5    0.05       0
Bank Sta=4990,5001.5
Exp/Cntr=0.3,0.1

Type RM Length L Ch R = 1,14000,500,500,500
BEGIN DESCRIPTION:
COTTONWOOD CREEK 28.0
END DESCRIPTION:
XS GIS Cut Line= 3
      2755805.70     10190003.08      2756017.20     10189595.94
      2755605.70     10188903.13
#Sta/Elev= 30
  4541.2 1320.14  4565.4 1319.67  4593.6 1318.86  4599.3 1317.80  4653.6 1315.20
  4760.7 1309.17  4762.2 1309.11  4831.3 1306.02  4868.0 1305.48  4925.4 1301.32
  4980.4 1298.76  4998.8 1296.15  5020.8 1295.71  5021.3 1295.21  5032.3 1295.71
  5053.8 1296.19  5061.4 1297.18  5069.4 1300.73  5075.2 1299.35  5090.8 1304.04
  5127.8 1305.71  5235.9 1305.43  5346.0 1306.74  5367.4 1308.18  5447.3 1310.35
  5549.9 1314.59  5573.2 1314.72  5638.3 1318.33  5724.4 1324.40  5805.8 1326.59
#Mann=7,-1,0
  4541.2    0.05       0  4565.4    0.12       0  4653.6    0.05       0
  4760.7    0.12       0  4762.2    0.05       0  5020.8    0.05       0
  5032.3    0.05       0
Bank Sta=5020.8,5032.3
Exp/Cntr=0.3,0.1

Type RM Length L Ch R = 1,13500,500,500,500
BEGIN DESCRIPTION:
COTTONWOOD CREEK 27.0
END DESCRIPTION:
XS GIS Cut Line= 3
      2756255.69     10190253.10      2756435.34     10189857.47
      2756855.69     10189653.11
#Sta/Elev= 30
  4565.5 1319.22  4608.4 1315.78  4642.4 1314.76  4649.0 1315.74  4654.5 1313.42
  4672.1 1313.24  4677.6 1310.60  4686.4 1308.73  4695.1 1308.88  4700.6 1306.84
  4718.2 1306.53  4723.7 1304.89  4763.2 1306.31  4792.9 1305.90  4839.1 1303.58
  4844.6 1302.61  4890.7 1301.39  4949.9 1297.61  4982.6 1293.16  4983.1 1292.66
  4994.4 1293.16  4999.6 1293.97  5019.2 1294.14  5033.7 1296.45  5069.9 1297.17
  5100.5 1301.39  5246.7 1303.03  5311.7 1305.37  5460.4 1315.30  5467.4 1315.73
#Mann=7,-1,0
  4565.5    0.05       0  4608.4    0.12       0  4686.4    0.05       0
  4982.6    0.05       0  4994.4    0.05       0  5246.7    0.12       0
  5460.4    0.05       0
Bank Sta=4982.6,4994.4
Exp/Cntr=0.3,0.1

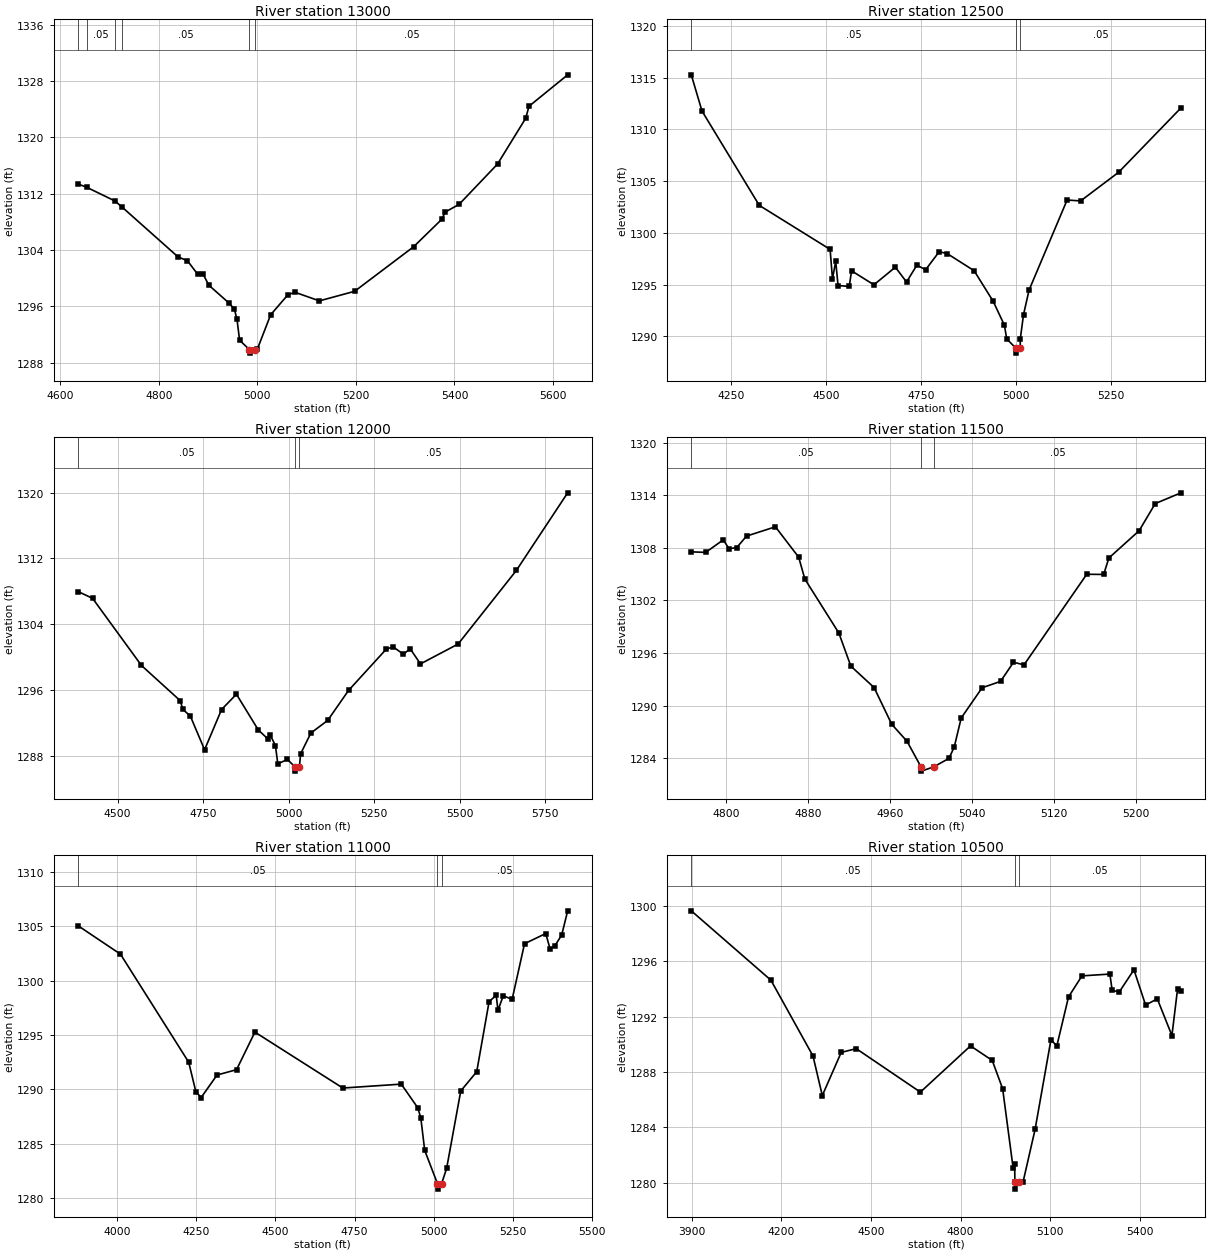
Type RM Length L Ch R = 1,13000,500,500,500
BEGIN DESCRIPTION:
COTTONWOOD CREEK 26.0
END DESCRIPTION:
XS GIS Cut Line= 3
      2756405.72     10190353.10      2756749.91     10190234.65
      2757155.68     10189753.12
#Sta/Elev= 30
  4636.0 1313.39  4653.7 1312.92  4711.0 1310.97  4725.8 1310.08  4839.0 1303.02
  4858.1 1302.47  4879.2 1300.52  4889.8 1300.58  4901.4 1299.00  4942.7 1296.44
  4953.2 1295.60  4958.6 1294.16  4963.9 1291.17  4983.9 1289.84  4984.4 1289.34
  4995.8 1289.84  5000.0 1289.92  5026.9 1294.79  5062.1 1297.65  5076.4 1297.99
  5125.8 1296.77  5197.3 1298.13  5317.0 1304.46  5374.2 1308.37  5381.2 1309.40
  5409.3 1310.49  5487.3 1316.22  5544.5 1322.73  5551.2 1324.44  5629.7 1328.91
#Mann=6,-1,0
  4636.0    0.12       0  4653.7    0.05       0  4711.0    0.12       0
  4725.8    0.05       0  4983.9    0.03       0  4995.8    0.05       0
Bank Sta=4983.9,4995.8
Exp/Cntr=0.3,0.1

Type RM Length L Ch R = 1,12500,500,500,500
BEGIN DESCRIPTION:
COTTONWOOD CREEK 25.0
END DESCRIPTION:
XS GIS Cut Line= 3
      2756505.71     10190953.09      2757197.27     10190451.01
      2757455.70     10190103.09
#Sta/Elev= 30
  4145.4 1315.27  4173.6 1311.77  4324.3 1302.66  4510.6 1298.41  4516.8 1295.56
  4525.3 1297.25  4531.5 1294.92  4560.9 1294.83  4567.0 1296.34  4625.8 1294.99
  4682.2 1296.69  4711.6 1295.26  4738.7 1296.88  4761.9 1296.45  4797.4 1298.18
  4818.3 1298.01  4889.4 1296.35  4939.6 1293.39  4969.0 1291.09  4975.2 1289.76
  4998.7 1288.89  4999.2 1288.39  5010.6 1288.89  5010.9 1289.77  5019.3 1292.10
  5033.9 1294.48  5134.0 1303.18  5169.5 1303.09  5269.6 1305.86  5433.4 1312.07
#Mann=3,-1,0
  4145.4    0.05       0  4998.7    0.05       0  5010.6    0.05       0
Bank Sta=4998.7,5010.6
Exp/Cntr=0.3,0.1

Type RM Length L Ch R = 1,12000,500,500,500
BEGIN DESCRIPTION:
COTTONWOOD CREEK 24.0
END DESCRIPTION:
XS GIS Cut Line= 3
      2756955.69     10191253.11      2757440.75     10190873.89
      2758255.72     10190903.11
#Sta/Elev= 30
  4384.3 1307.98  4426.8 1307.15  4569.7 1298.98  4683.6 1294.67  4690.0 1293.66
  4712.6 1292.82  4754.2 1288.72  4803.9 1293.62  4847.3 1295.48  4911.5 1291.11
  4940.4 1290.00  4946.8 1290.46  4961.3 1289.22  4968.2 1287.01  4996.5 1287.54
  5018.7 1286.62  5019.2 1286.12  5031.3 1286.62  5035.0 1288.24  5065.0 1290.76
  5114.0 1292.29  5175.0 1295.94  5285.1 1300.96  5305.1 1301.25  5335.2 1300.35
  5355.2 1301.01  5385.2 1299.17  5495.3 1301.59  5665.4 1310.54  5815.5 1319.99
#Mann=3,-1,0
  4384.3    0.05       0  5018.7    0.05       0  5031.3    0.05       0
Bank Sta=5018.7,5031.3
Exp/Cntr=0.3,0.1

Type RM Length L Ch R = 1,11500,500,500,500
BEGIN DESCRIPTION:
COTTONWOOD CREEK 23.0
END DESCRIPTION:
XS GIS Cut Line= 3
      2757405.71     10191403.10      2757616.60     10191302.39
      2757855.67     10191253.11
#Sta/Elev= 30
  4766.3 1307.55  4780.4 1307.49  4797.5 1308.92  4803.1 1307.91  4810.6 1308.03
  4820.2 1309.35  4848.4 1310.41  4871.1 1306.94  4877.1 1304.45  4910.3 1298.28
  4922.0 1294.50  4944.7 1292.05  4961.9 1287.86  4976.8 1285.92  4990.4 1283.01
  4990.9 1282.51  5003.1 1283.01  5017.8 1283.97  5022.9 1285.27  5029.7 1288.58
  5050.1 1292.03  5068.1 1292.76  5080.7 1294.94  5091.0 1294.65  5152.2 1304.99
  5168.7 1304.97  5173.8 1306.85  5203.3 1309.96  5219.0 1313.06  5244.1 1314.29
#Mann=3,-1,0
  4766.3    0.05       0  4990.4    0.03       0  5003.1    0.05       0
Bank Sta=4990.4,5003.1
Exp/Cntr=0.3,0.1

Type RM Length L Ch R = 1,11000,500,500,500
BEGIN DESCRIPTION:
COTTONWOOD CREEK 22.0
END DESCRIPTION:
XS GIS Cut Line= 3
      2756905.72     10192203.09      2757911.08     10191701.81
      2758100.07     10191323.16
#Sta/Elev= 30
  3876.6 1305.07  4010.6 1302.45  4226.2 1292.50  4248.6 1289.80  4265.4 1289.24
  4315.7 1291.32  4377.3 1291.81  4435.3 1295.27  4713.0 1290.12  4897.6 1290.48
  4949.3 1288.32  4959.2 1287.40  4971.6 1284.38  5012.0 1281.31  5012.5 1280.81
  5024.8 1281.31  5040.8 1282.71  5085.5 1289.85  5135.9 1291.62  5175.0 1298.08
  5197.4 1298.66  5203.0 1297.28  5219.8 1298.62  5247.7 1298.28  5286.9 1303.41
  5354.0 1304.35  5367.4 1302.95  5382.0 1303.19  5404.3 1304.21  5423.2 1306.44
#Mann=3,-1,0
  3876.6    0.05       0  5012.0    0.05       0  5024.8    0.05       0
Bank Sta=5012,5024.8
Exp/Cntr=0.3,0.1

Type RM Length L Ch R = 1,10500,500,500,500
BEGIN DESCRIPTION:
COTTONWOOD CREEK 21.0
END DESCRIPTION:
XS GIS Cut Line= 3
      2757051.51     10192406.44      2758116.67     10192122.71
      2758634.77     10191975.90
#Sta/Elev= 30
  3897.7 1299.64  4164.5 1294.63  4305.6 1289.15  4336.7 1286.29  4400.1 1289.41
  4450.5 1289.68  4665.4 1286.54  4833.4 1289.88  4906.2 1288.83  4941.1 1286.78
  4976.1 1281.07  4981.2 1281.38  4982.2 1280.03  4982.7 1279.53  4995.0 1280.03
  5009.4 1280.04  5049.7 1283.84  5102.9 1290.32  5122.7 1289.88  5161.8 1293.42
  5206.9 1294.94  5300.4 1295.07  5308.0 1293.90  5331.6 1293.77  5381.0 1295.38
  5420.1 1292.83  5459.3 1293.28  5508.3 1290.63  5527.1 1293.97  5538.5 1293.86
#Mann=3,-1,0
  3897.7    0.05       0  4982.2    0.03       0  4995.0    0.05       0
Bank Sta=4982.2,4995
Exp/Cntr=0.3,0.1

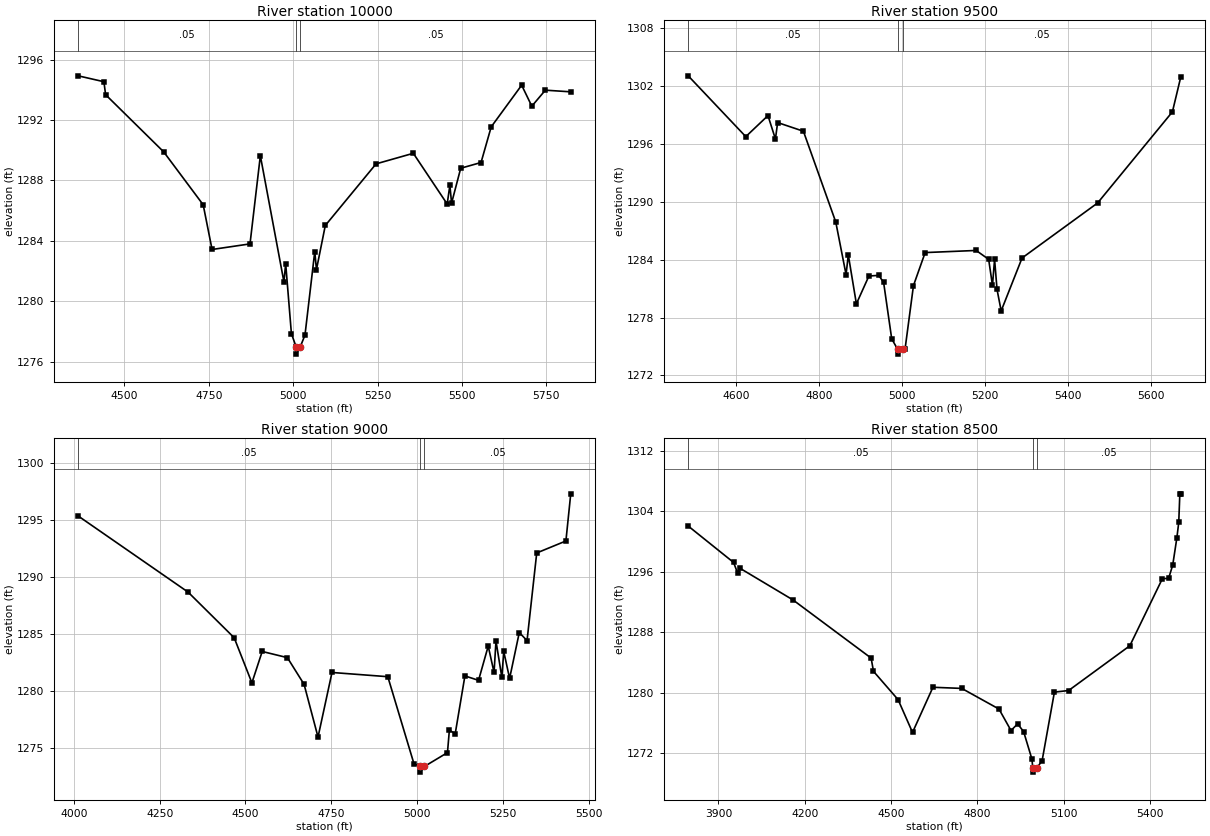
Type RM Length L Ch R = 1,10000,500,500,500
BEGIN DESCRIPTION:
COTTONWOOD CREEK 20.0
END DESCRIPTION:
XS GIS Cut Line= 3
      2757337.58     10192724.09      2757960.69     10192593.22
      2758780.66     10192531.45
#Sta/Elev= 30
  4363.3 1294.92  4439.5 1294.53  4444.6 1293.67  4616.8 1289.88  4733.6 1286.38
  4759.9 1283.42  4872.3 1283.79  4902.9 1289.63  4972.8 1281.27  4977.9 1282.49
  4994.9 1277.85  5008.6 1276.99  5009.1 1276.49  5021.4 1276.99  5035.1 1277.75
  5064.1 1283.28  5069.1 1282.09  5095.3 1285.01  5245.7 1289.09  5356.0 1289.79
  5456.3 1286.43  5464.3 1287.68  5469.3 1286.49  5496.4 1288.80  5556.6 1289.18
  5586.7 1291.54  5676.9 1294.30  5707.0 1292.91  5747.1 1293.97  5822.3 1293.86
#Mann=3,-1,0
  4363.3    0.05       0  5008.6    0.03       0  5021.4    0.05       0
Bank Sta=5008.6,5021.4
Exp/Cntr=0.3,0.1

Type RM Length L Ch R = 1,9500,500,500,500
BEGIN DESCRIPTION:
COTTONWOOD CREEK 19.0
END DESCRIPTION:
XS GIS Cut Line= 3
      2757505.69     10192903.11      2757988.25     10193085.29
      2758655.71     10193003.11
#Sta/Elev= 30
  4484.2 1303.04  4623.1 1296.74  4676.6 1298.92  4694.6 1296.49  4699.9 1298.20
  4762.1 1297.30  4840.2 1287.89  4865.0 1282.45  4870.4 1284.49  4889.9 1279.42
  4920.1 1282.30  4943.8 1282.37  4955.6 1281.64  4975.1 1275.80  4989.4 1274.71
  4989.9 1274.21  5002.5 1274.71  5007.5 1274.79  5027.6 1281.31  5055.8 1284.73
  5178.8 1284.95  5209.0 1284.03  5218.2 1281.33  5223.3 1284.03  5229.2 1280.91
  5239.2 1278.69  5289.6 1284.17  5471.9 1289.87  5652.3 1299.31  5672.5 1302.93
#Mann=3,-1,0
  4484.2    0.05       0  4989.4    0.05       0  5002.5    0.05       0
Bank Sta=4989.4,5002.5
Exp/Cntr=0.3,0.1

Type RM Length L Ch R = 1,9000,500,500,500
BEGIN DESCRIPTION:
COTTONWOOD CREEK 18.0
END DESCRIPTION:
XS GIS Cut Line= 3
      2757905.68     10194403.14      2758152.44     10193447.07
      2758555.71     10193253.10
#Sta/Elev= 30
  4012.6 1295.35  4332.8 1288.68  4467.1 1284.68  4518.7 1280.73  4548.7 1283.48
  4622.0 1282.94  4670.7 1280.60  4711.3 1275.98  4752.0 1281.64  4914.6 1281.27
  4990.8 1273.64  5008.0 1273.41  5008.5 1272.91  5021.4 1273.41  5088.4 1274.62
  5093.9 1276.58  5111.0 1276.28  5139.2 1281.34  5178.9 1280.95  5207.1 1283.95
  5224.1 1281.64  5229.7 1284.40  5246.8 1281.21  5252.3 1283.48  5269.4 1281.12
  5297.6 1285.14  5320.2 1284.43  5348.4 1292.11  5433.4 1293.16  5447.5 1297.29
#Mann=3,-1,0
  4012.6    0.05       0  5008.0    0.05       0  5021.4    0.05       0
Bank Sta=5008,5021.4
Exp/Cntr=0.3,0.1

Type RM Length L Ch R = 1,8500,500,500,500
BEGIN DESCRIPTION:
COTTONWOOD CREEK 17.0
END DESCRIPTION:
XS GIS Cut Line= 3
      2757855.68     10194603.12      2758574.26     10193635.94
      2758955.67     10193303.13
#Sta/Elev= 30
  3795.1 1302.03  3952.6 1297.22  3967.2 1295.77  3973.5 1296.48  4159.1 1292.26
  4430.5 1284.57  4438.7 1282.82  4524.2 1279.07  4574.3 1274.74  4645.2 1280.71
  4745.3 1280.56  4874.7 1277.83  4916.4 1274.99  4939.4 1275.87  4960.2 1274.85
  4989.4 1271.17  4991.9 1269.99  4992.4 1269.49  5005.3 1269.99  5024.5 1271.01
  5067.2 1280.07  5116.5 1280.28  5329.2 1286.20  5442.1 1295.06  5464.0 1295.12
  5478.2 1296.87  5492.5 1300.45  5499.1 1302.50  5502.9 1306.29  5506.2 1306.29
#Mann=3,-1,0
  3795.1    0.05       0  4991.9    0.05       0  5005.3    0.05       0
Bank Sta=4991.9,5005.3
Exp/Cntr=0.3,0.1