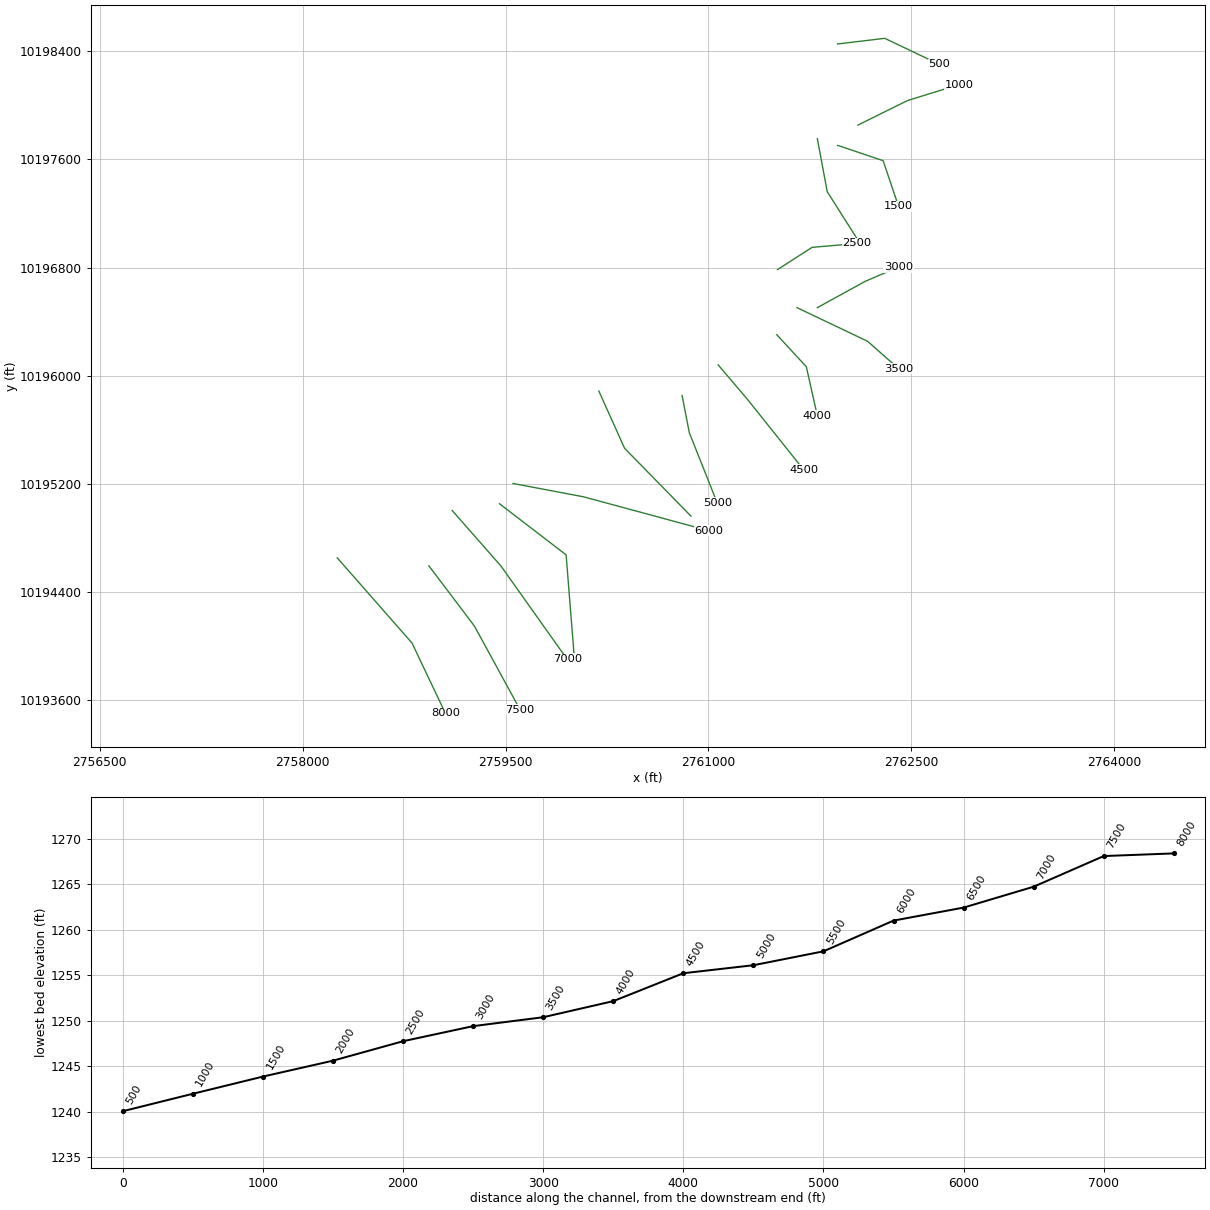
HEC-RAS study COTTONWOOD CREEK.prj: COTTONWOOD CREEK Base Level Engineering

--- COTTONWOOD CREEK.g01 (geometry) --- (continued)

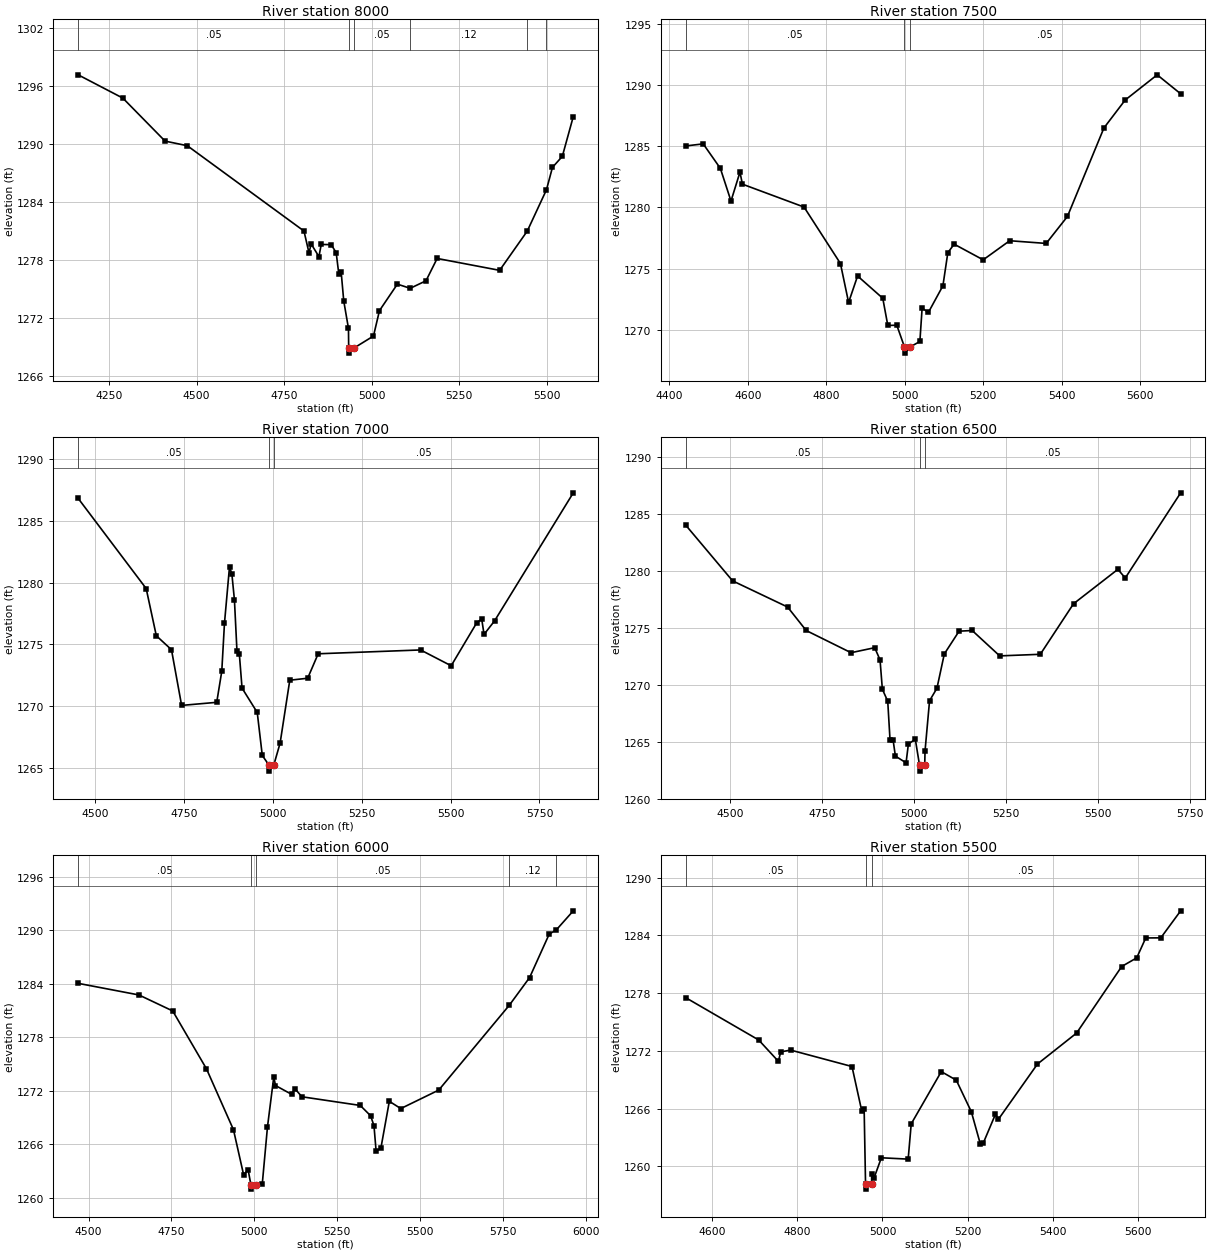
Type RM Length L Ch R = 1,8000,500,500,500
BEGIN DESCRIPTION:
COTTONWOOD CREEK 16.0
END DESCRIPTION:
XS GIS Cut Line= 3
      2758255.71     10194653.09      2758808.82     10194023.03
      2759055.66     10193503.15
#Sta/Elev= 30
  4161.6 1297.20  4289.2 1294.79  4409.7 1290.34  4473.3 1289.86  4806.4 1281.03
  4820.6 1278.80  4827.2 1279.68  4849.1 1278.38  4855.7 1279.64  4884.2 1279.62
  4898.4 1278.79  4906.0 1276.55  4912.6 1276.79  4920.0 1273.79  4933.5 1270.95
  4934.1 1268.89  4934.6 1268.39  4948.0 1268.89  5004.9 1270.16  5022.0 1272.79
  5073.1 1275.53  5109.8 1275.10  5154.9 1275.88  5186.7 1278.19  5365.2 1276.96
  5444.0 1281.02  5498.9 1285.30  5516.0 1287.62  5544.2 1288.76  5575.5 1292.88
#Mann=6,-1,0
  4161.6    0.05       0  4934.1    0.05       0  4948.0    0.05       0
  5109.8    0.12       0  5444.0    0.05       0  5498.9    0.12       0
Bank Sta=4934.1,4948
Exp/Cntr=0.3,0.1

Type RM Length L Ch R = 1,7500,500,500,500
BEGIN DESCRIPTION:
COTTONWOOD CREEK 15.0
END DESCRIPTION:
XS GIS Cut Line= 3
      2758933.45     10194593.92      2759270.36     10194148.48
      2759607.03     10193531.45
#Sta/Elev= 30
  4441.5 1285.02  4486.5 1285.19  4530.2 1283.19  4557.3 1280.52  4580.1 1282.88
  4586.4 1281.90  4743.4 1280.03  4836.1 1275.42  4856.9 1272.24  4879.8 1274.40
  4944.0 1272.58  4956.8 1270.36  4979.7 1270.38  4999.3 1268.60  4999.8 1268.10
  5013.2 1268.60  5038.5 1269.05  5044.2 1271.77  5060.3 1271.43  5097.2 1273.60
  5109.7 1276.30  5125.8 1277.00  5199.8 1275.72  5267.3 1277.28  5360.3 1277.06
  5414.4 1279.26  5507.4 1286.49  5561.5 1288.77  5643.1 1290.83  5702.9 1289.28
#Mann=3,-1,0
  4441.5    0.05       0  4999.3    0.05       0  5013.2    0.05       0
Bank Sta=4999.3,5013.2
Exp/Cntr=0.3,0.1

Type RM Length L Ch R = 1,7000,500,500,500
BEGIN DESCRIPTION:
COTTONWOOD CREEK 14.0
END DESCRIPTION:
XS GIS Cut Line= 3
      2759105.69     10195003.11      2759466.68     10194592.27
      2759955.67     10193903.13
#Sta/Elev= 30
  4453.1 1286.81  4644.3 1279.51  4672.8 1275.69  4715.4 1274.56  4743.9 1270.05
  4842.6 1270.30  4856.8 1272.81  4864.4 1276.71  4878.6 1281.29  4885.3 1280.66
  4892.4 1278.59  4899.5 1274.45  4906.2 1274.20  4913.8 1271.45  4956.5 1269.48
  4970.7 1266.00  4989.1 1265.23  4989.6 1264.73  5003.1 1265.23  5020.8 1267.00
  5048.0 1272.09  5098.3 1272.25  5127.8 1274.23  5415.7 1274.54  5501.7 1273.26
  5573.2 1276.72  5587.5 1277.05  5594.1 1275.80  5623.6 1276.89  5845.0 1287.26
#Mann=3,-1,0
  4453.1    0.05       0  4989.1    0.05       0  5003.1    0.05       0
Bank Sta=4989.1,5003.1
Exp/Cntr=0.3,0.1

Type RM Length L Ch R = 1,6500,500,500,500
BEGIN DESCRIPTION:
COTTONWOOD CREEK 13.0
END DESCRIPTION:
XS GIS Cut Line= 3
      2759455.70     10195053.10      2759948.08     10194675.17
      2760005.69     10193953.07
#Sta/Elev= 30
  4379.3 1284.05  4507.1 1279.14  4656.6 1276.84  4707.0 1274.78  4828.9 1272.83
  4893.2 1273.27  4907.7 1272.20  4914.0 1269.62  4928.6 1268.57  4934.9 1265.13
  4943.1 1265.17  4949.4 1263.75  4978.4 1263.16  4984.7 1264.81  5003.5 1265.23
  5015.1 1262.93  5015.6 1262.43  5029.1 1262.93  5029.9 1264.19  5042.2 1268.61
  5062.3 1269.71  5082.3 1272.72  5122.4 1274.72  5158.0 1274.78  5232.8 1272.55
  5343.1 1272.69  5433.4 1277.13  5553.8 1280.15  5573.9 1279.39  5724.4 1286.87
#Mann=3,-1,0
  4379.3    0.05       0  5015.1    0.05       0  5029.1    0.05       0
Bank Sta=5015.1,5029.1
Exp/Cntr=0.3,0.1

Type RM Length L Ch R = 1,6000,500,500,500
BEGIN DESCRIPTION:
COTTONWOOD CREEK 12.0
END DESCRIPTION:
XS GIS Cut Line= 3
      2759555.66     10195203.12      2760077.59     10195104.31
      2761005.69     10194853.11
#Sta/Elev= 30
  4468.8 1284.04  4652.0 1282.74  4753.8 1280.95  4855.6 1274.47  4937.0 1267.65
  4967.5 1262.62  4981.2 1263.16  4989.5 1261.50  4990.0 1261.00  5003.5 1261.50
  5023.8 1261.57  5039.5 1267.96  5058.5 1273.55  5063.7 1272.60  5112.0 1271.62
  5122.3 1272.24  5143.4 1271.34  5319.2 1270.37  5350.3 1269.22  5360.6 1268.11
  5367.0 1265.27  5381.3 1265.56  5406.9 1270.83  5441.5 1270.02  5555.9 1272.09
  5768.6 1281.59  5829.8 1284.69  5889.0 1289.56  5910.4 1290.03  5961.5 1292.16
#Mann=5,-1,0
  4468.8    0.05       0  4989.5    0.05       0  5003.5    0.05       0
  5768.6    0.12       0  5910.4    0.05       0
Bank Sta=4989.5,5003.5
Exp/Cntr=0.3,0.1

Type RM Length L Ch R = 1,5500,500,500,500
BEGIN DESCRIPTION:
COTTONWOOD CREEK 11.0
END DESCRIPTION:
XS GIS Cut Line= 3
      2760190.36     10195885.64      2760380.42     10195463.34
      2760870.80     10194962.13
#Sta/Elev= 30
  4536.9 1277.54  4708.9 1273.13  4755.2 1270.91  4760.7 1271.89  4783.9 1272.08
  4928.3 1270.37  4951.4 1265.72  4956.9 1265.93  4960.2 1258.12  4960.7 1257.62
  4974.5 1258.12  4974.6 1259.18  4980.0 1258.76  4997.4 1260.88  5060.4 1260.74
  5067.6 1264.41  5138.3 1269.84  5173.6 1268.95  5209.0 1265.66  5230.2 1262.30
  5237.3 1262.44  5265.6 1265.40  5272.6 1264.88  5364.5 1270.63  5456.5 1273.85
  5562.5 1280.77  5597.9 1281.67  5619.1 1283.74  5654.5 1283.75  5701.2 1286.56
#Mann=3,-1,0
  4536.9    0.05       0  4960.2    0.03       0  4974.5    0.05       0
Bank Sta=4960.2,4974.5
Exp/Cntr=0.3,0.1

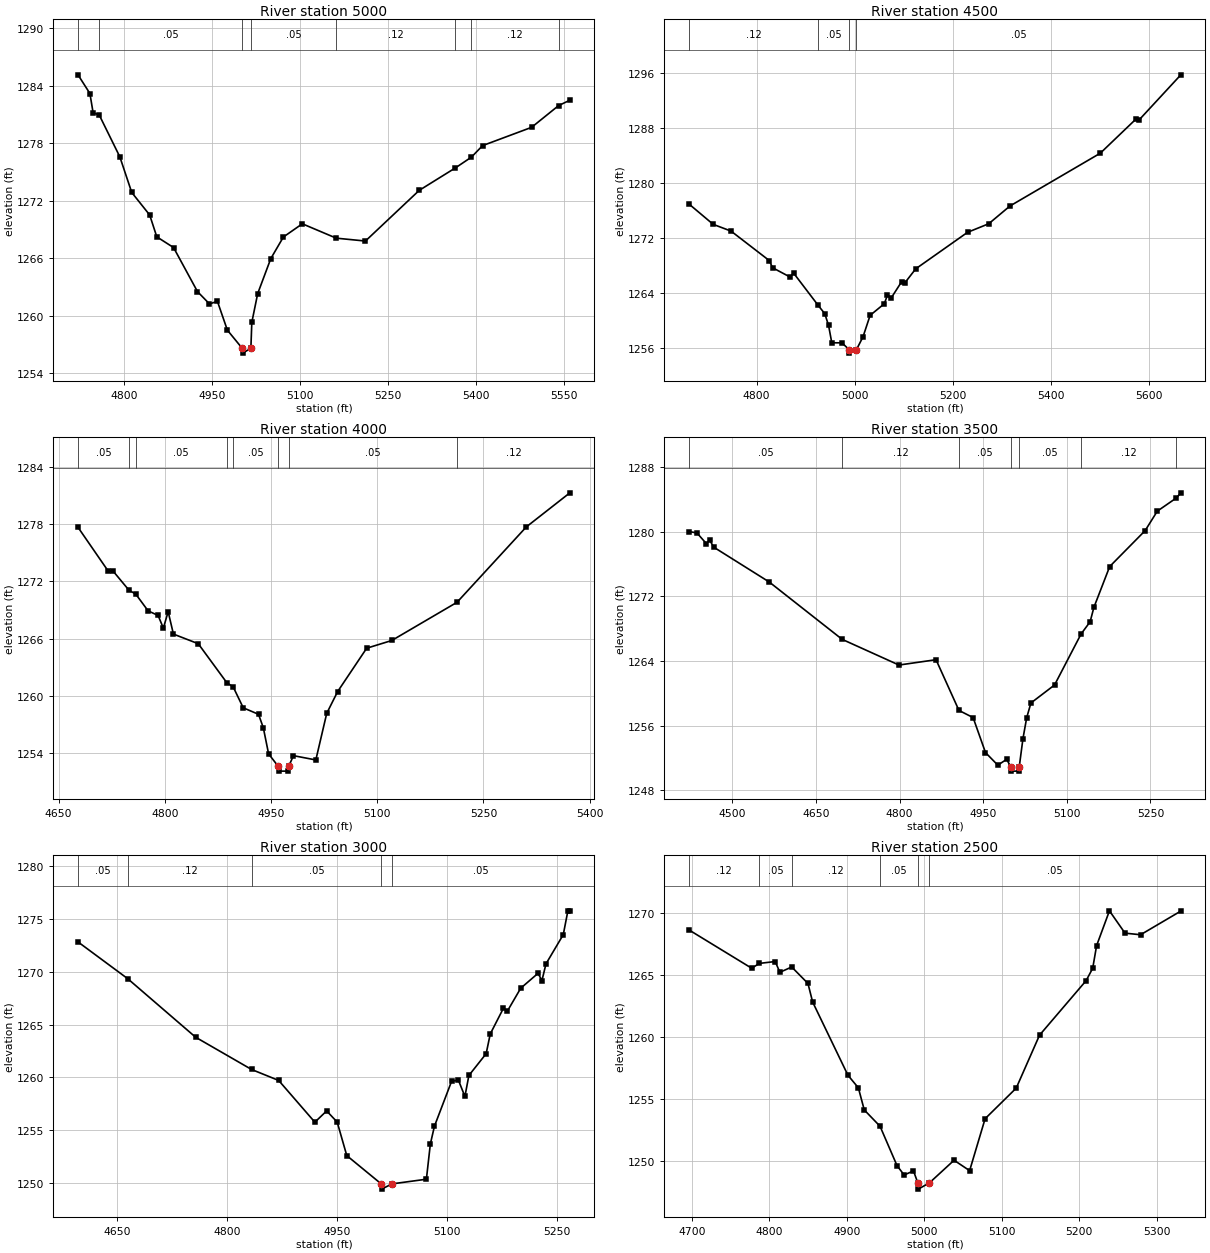
Type RM Length L Ch R = 1,5000,500,500,500
BEGIN DESCRIPTION:
COTTONWOOD CREEK 10.0
END DESCRIPTION:
XS GIS Cut Line= 3
      2760805.69     10195853.07      2760858.85     10195579.28
      2761065.39     10195059.19
#Sta/Elev= 30
  4721.1 1285.14  4741.4 1283.19  4746.9 1281.16  4757.1 1280.97  4792.4 1276.58
  4812.7 1272.86  4843.3 1270.51  4855.4 1268.23  4884.0 1267.11  4924.8 1262.51
  4945.2 1261.23  4958.8 1261.49  4975.7 1258.49  5001.1 1256.59  5001.6 1256.09
  5015.8 1256.59  5017.4 1259.30  5027.4 1262.30  5049.7 1265.95  5071.2 1268.21
  5103.5 1269.59  5161.4 1268.09  5211.1 1267.79  5302.8 1273.08  5364.6 1275.43
  5391.8 1276.55  5410.8 1277.75  5494.4 1279.66  5540.4 1281.93  5559.6 1282.49
#Mann=8,-1,0
  4721.1    0.12       0  4757.1    0.05       0  5001.1    0.05       0
  5015.8    0.05       0  5161.4    0.12       0  5364.6    0.05       0
  5391.8    0.12       0  5540.4    0.05       0
Bank Sta=5001.1,5015.8
Exp/Cntr=0.3,0.1

Type RM Length L Ch R = 1,4500,500,500,500
BEGIN DESCRIPTION:
COTTONWOOD CREEK 9.0
END DESCRIPTION:
XS GIS Cut Line= 3
      2761072.31     10196080.07      2761291.05     10195822.66
      2761705.67     10195303.12
#Sta/Elev= 30
  4662.2 1276.96  4711.6 1273.99  4747.9 1273.01  4825.9 1268.71  4832.5 1267.67
  4868.2 1266.31  4875.3 1266.90  4925.7 1262.16  4939.0 1260.96  4946.7 1259.26
  4953.3 1256.72  4974.1 1256.71  4988.7 1255.71  4989.2 1255.21  5003.5 1255.71
  5017.0 1257.60  5031.4 1260.72  5060.3 1262.41  5066.7 1263.66  5074.7 1263.29
  5095.5 1265.61  5101.9 1265.43  5124.3 1267.50  5230.0 1272.83  5273.2 1274.08
  5316.5 1276.67  5500.6 1284.37  5572.7 1289.31  5579.0 1289.17  5664.7 1295.80
#Mann=4,-1,0
  4662.2    0.12       0  4925.7    0.05       0  4988.7    0.03       0
  5003.5    0.05       0
Bank Sta=4988.7,5003.5
Exp/Cntr=0.3,0.1

Type RM Length L Ch R = 1,4000,500,500,500
BEGIN DESCRIPTION:
COTTONWOOD CREEK 8.0
END DESCRIPTION:
XS GIS Cut Line= 3
      2761505.68     10196303.12      2761724.41     10196066.13
      2761805.68     10195703.12
#Sta/Elev= 30
  4677.5 1277.67  4719.8 1273.12  4727.1 1273.08  4749.5 1271.08  4759.0 1270.68
  4776.5 1268.92  4790.6 1268.44  4798.0 1267.11  4804.8 1268.84  4812.2 1266.49
  4847.3 1265.48  4887.6 1261.40  4896.6 1260.96  4910.8 1258.77  4932.4 1258.09
  4939.2 1256.67  4946.6 1253.95  4960.2 1252.64  4960.7 1252.14  4974.5 1252.14
  4975.0 1252.64  4981.7 1253.76  5013.3 1253.31  5028.7 1258.19  5044.1 1260.47
  5085.1 1265.01  5120.6 1265.82  5212.7 1269.82  5310.5 1277.71  5372.0 1281.28
#Mann=8,-1,0
  4677.5    0.05       0  4749.5    0.12       0  4759.0    0.05       0
  4887.6    0.12       0  4896.6    0.05       0  4960.2    0.03       0
  4975.0    0.05       0  5212.7    0.12       0
Bank Sta=4960.2,4975
Exp/Cntr=0.3,0.1

Type RM Length L Ch R = 1,3500,500,500,500
BEGIN DESCRIPTION:
COTTONWOOD CREEK 7.0
END DESCRIPTION:
XS GIS Cut Line= 3
      2761655.64     10196503.13      2762177.25     10196254.34
      2762405.66     10196053.13
#Sta/Elev= 30
  4422.1 1280.04  4436.3 1279.88  4453.4 1278.54  4459.0 1279.01  4466.5 1278.11
  4566.2 1273.79  4696.9 1266.69  4798.8 1263.51  4865.3 1264.17  4906.4 1257.89
  4931.8 1257.00  4954.0 1252.67  4976.1 1251.11  4992.0 1251.83  4999.6 1250.87
  5000.1 1250.37  5014.0 1250.37  5014.5 1250.87  5021.2 1254.39  5027.9 1256.98
  5035.5 1258.81  5077.9 1261.04  5125.5 1267.36  5141.7 1268.87  5148.4 1270.64
  5176.8 1275.71  5240.4 1280.16  5262.2 1282.57  5296.5 1284.21  5304.4 1284.84
#Mann=7,-1,0
  4422.1    0.05       0  4696.9    0.12       0  4906.4    0.05       0
  4999.6    0.03       0  5014.5    0.05       0  5125.5    0.12       0
  5296.5    0.05       0
Bank Sta=4999.6,5014.5
Exp/Cntr=0.3,0.1

Type RM Length L Ch R = 1,3000,500,500,500
BEGIN DESCRIPTION:
COTTONWOOD CREEK 6.0
END DESCRIPTION:
XS GIS Cut Line= 3
      2761805.66     10196503.10      2762159.52     10196697.81
      2762405.65     10196803.10
#Sta/Elev= 30
  4596.1 1272.84  4664.0 1269.35  4756.7 1263.80  4833.1 1260.74  4870.1 1259.70
  4919.5 1255.74  4935.6 1256.81  4950.0 1255.75  4963.1 1252.57  5010.1 1249.89
  5010.6 1249.39  5025.0 1249.89  5071.8 1250.33  5077.2 1253.67  5082.8 1255.36
  5106.2 1259.62  5115.5 1259.73  5124.4 1258.18  5129.8 1260.17  5153.4 1262.24
  5159.0 1264.11  5177.0 1266.55  5182.5 1266.29  5200.6 1268.45  5224.2 1269.86
  5229.6 1269.18  5235.1 1270.76  5258.7 1273.53  5265.0 1275.79  5267.7 1275.79
#Mann=5,-1,0
  4596.1    0.05       0  4664.0    0.12       0  4833.1    0.05       0
  5010.1    0.03       0  5025.0    0.05       0
Bank Sta=5010.1,5025
Exp/Cntr=0.3,0.1

Type RM Length L Ch R = 1,2500,500,500,500
BEGIN DESCRIPTION:
COTTONWOOD CREEK 5.0
END DESCRIPTION:
XS GIS Cut Line= 3
      2761511.57     10196784.93      2761767.35     10196949.05
      2762097.51     10196977.63
#Sta/Elev= 30
  4696.1 1268.64  4777.1 1265.55  4787.1 1265.94  4807.5 1266.09  4813.5 1265.22
  4828.8 1265.65  4849.8 1264.32  4855.8 1262.83  4901.4 1256.92  4914.9 1255.90
  4922.5 1254.12  4942.9 1252.80  4964.8 1249.63  4974.0 1248.87  4986.1 1249.20
  4991.7 1248.23  4992.2 1247.73  5006.6 1248.23  5038.5 1250.06  5058.6 1249.22
  5078.6 1253.41  5118.8 1255.88  5148.9 1260.15  5209.1 1264.55  5217.6 1265.55
  5222.6 1267.37  5239.2 1270.18  5259.3 1268.38  5279.4 1268.25  5331.4 1270.16
#Mann=6,-1,0
  4696.1    0.12       0  4787.1    0.05       0  4828.8    0.12       0
  4942.9    0.05       0  4991.7    0.03       0  5006.6    0.05       0
Bank Sta=4991.7,5006.6
Exp/Cntr=0.3,0.1

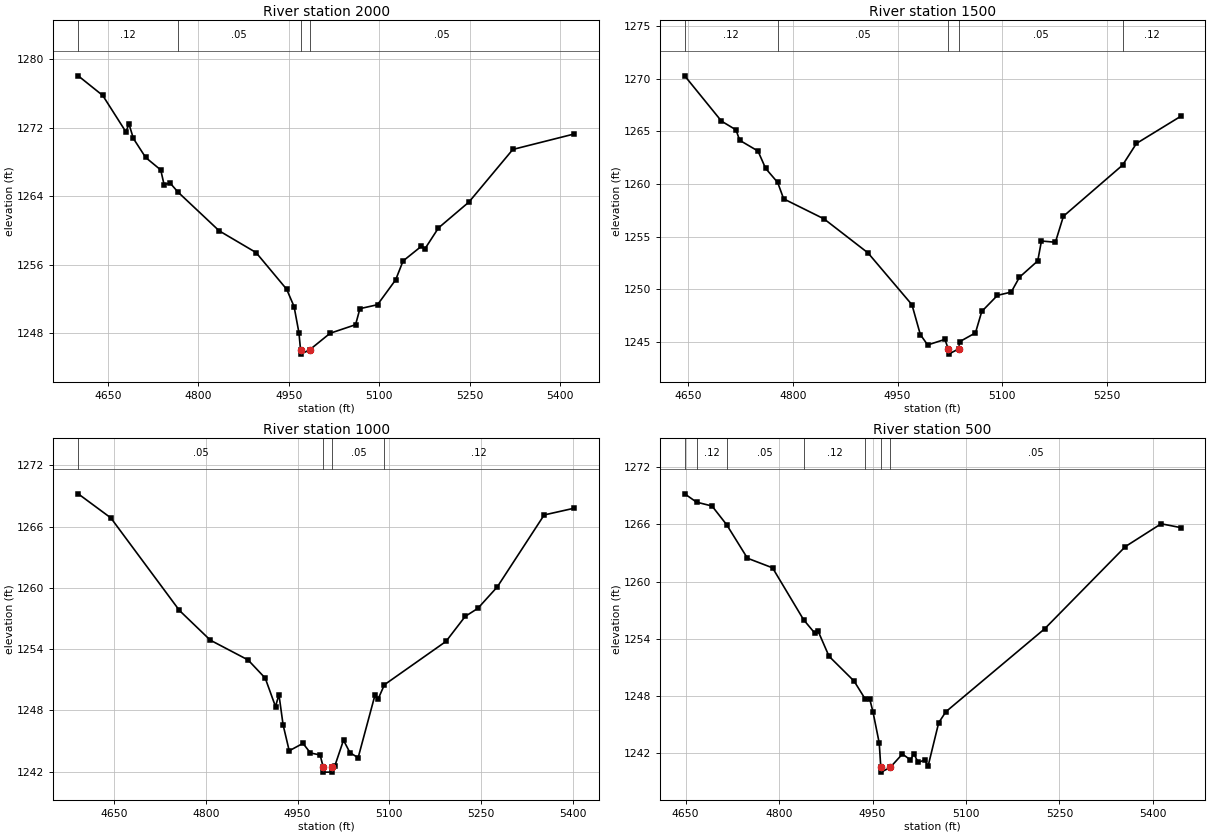
Type RM Length L Ch R = 1,2000,500,500,500
BEGIN DESCRIPTION:
COTTONWOOD CREEK 4.0
END DESCRIPTION:
XS GIS Cut Line= 3
      2761805.69     10197753.10      2761878.75     10197360.64
      2762105.70     10197003.09
#Sta/Elev= 30
  4600.8 1278.03  4641.5 1275.74  4679.9 1271.50  4685.0 1272.42  4692.3 1270.73
  4712.7 1268.51  4737.7 1267.06  4743.2 1265.36  4753.4 1265.52  4766.3 1264.48
  4834.7 1259.96  4895.8 1257.43  4946.6 1253.15  4958.9 1251.13  4967.0 1248.06
  4969.6 1246.09  4970.1 1245.59  4984.7 1246.09  5018.6 1248.02  5060.9 1249.02
  5068.1 1250.89  5097.3 1251.35  5127.4 1254.25  5139.7 1256.45  5170.2 1258.17
  5176.1 1257.88  5198.4 1260.30  5249.0 1263.32  5321.8 1269.45  5423.5 1271.25
#Mann=4,-1,0
  4600.8    0.12       0  4766.3    0.05       0  4969.6    0.03       0
  4984.7    0.05       0
Bank Sta=4969.6,4984.7
Exp/Cntr=0.3,0.1

Type RM Length L Ch R = 1,1500,500,500,500
BEGIN DESCRIPTION:
COTTONWOOD CREEK 3.0
END DESCRIPTION:
XS GIS Cut Line= 3
      2761955.70     10197703.11      2762292.20     10197590.00
      2762405.69     10197253.10
#Sta/Elev= 30
  4645.0 1270.26  4697.7 1265.96  4718.5 1265.13  4723.8 1264.14  4750.0 1263.12
  4761.0 1261.47  4778.2 1260.14  4786.8 1258.58  4844.6 1256.68  4907.6 1253.45
  4970.6 1248.53  4982.6 1245.70  4993.1 1244.71  5017.8 1245.24  5022.6 1244.34
  5023.1 1243.84  5037.7 1244.34  5038.9 1245.02  5061.6 1245.86  5070.6 1247.89
  5093.1 1249.42  5112.8 1249.73  5124.6 1251.14  5150.8 1252.69  5156.1 1254.58
  5176.1 1254.46  5187.6 1256.93  5272.3 1261.78  5292.2 1263.84  5355.5 1266.41
#Mann=5,-1,0
  4645.0    0.12       0  4778.2    0.05       0  5022.6    0.03       0
  5037.7    0.05       0  5272.3    0.12       0
Bank Sta=5022.6,5037.7
Exp/Cntr=0.3,0.1

Type RM Length L Ch R = 1,1000,500,500,500
BEGIN DESCRIPTION:
COTTONWOOD CREEK 2.0
END DESCRIPTION:
XS GIS Cut Line= 3
      2762105.67     10197853.11      2762471.66     10198034.33
      2762855.71     10198153.12
#Sta/Elev= 30
  4591.6 1269.22  4644.9 1266.86  4757.0 1257.79  4807.5 1254.88  4869.2 1252.94
  4897.2 1251.16  4914.0 1248.37  4919.6 1249.55  4926.4 1246.58  4936.4 1244.04
  4958.9 1244.77  4971.0 1243.83  4986.9 1243.63  4991.9 1242.45  4992.4 1241.95
  5006.5 1241.95  5007.0 1242.45  5011.1 1242.59  5025.1 1245.08  5035.6 1243.86
  5049.0 1243.36  5076.4 1249.47  5081.6 1249.10  5091.9 1250.51  5192.6 1254.76
  5224.0 1257.21  5244.7 1258.00  5276.4 1260.10  5353.0 1267.15  5402.0 1267.81
#Mann=4,-1,0
  4591.6    0.05       0  4991.9    0.05       0  5007.0    0.05       0
  5091.9    0.12       0
Bank Sta=4991.9,5007
Exp/Cntr=0.3,0.1

Type RM Length L Ch R = 1,500,0,0,0
BEGIN DESCRIPTION:
COTTONWOOD CREEK 1.0
END DESCRIPTION:
XS GIS Cut Line= 3
      2761955.65     10198453.11      2762304.60     10198494.57
      2762705.65     10198303.13
#Sta/Elev= 30
  4648.6 1269.21  4667.6 1268.34  4692.5 1267.93  4716.1 1265.96  4749.3 1262.46
  4789.6 1261.45  4839.5 1256.00  4857.8 1254.57  4862.8 1254.80  4880.2 1252.18
  4920.5 1249.57  4938.4 1247.68  4945.5 1247.70  4950.7 1246.36  4960.8 1243.08
  4963.3 1240.53  4963.8 1240.03  4978.5 1240.53  4998.0 1241.93  5010.9 1241.31
  5016.4 1241.94  5023.4 1241.04  5033.6 1241.31  5039.1 1240.64  5056.2 1245.21
  5067.7 1246.36  5226.1 1255.05  5355.8 1263.68  5413.2 1266.07  5444.4 1265.67
#Mann=7,-1,0
  4648.6    0.05       0  4667.6    0.12       0  4716.1    0.05       0
  4839.5    0.12       0  4938.4    0.05       0  4963.3    0.03       0
  4978.5    0.05       0
Bank Sta=4963.3,4978.5
Exp/Cntr=0.3,0.1

Chan Stop Cuts=-1