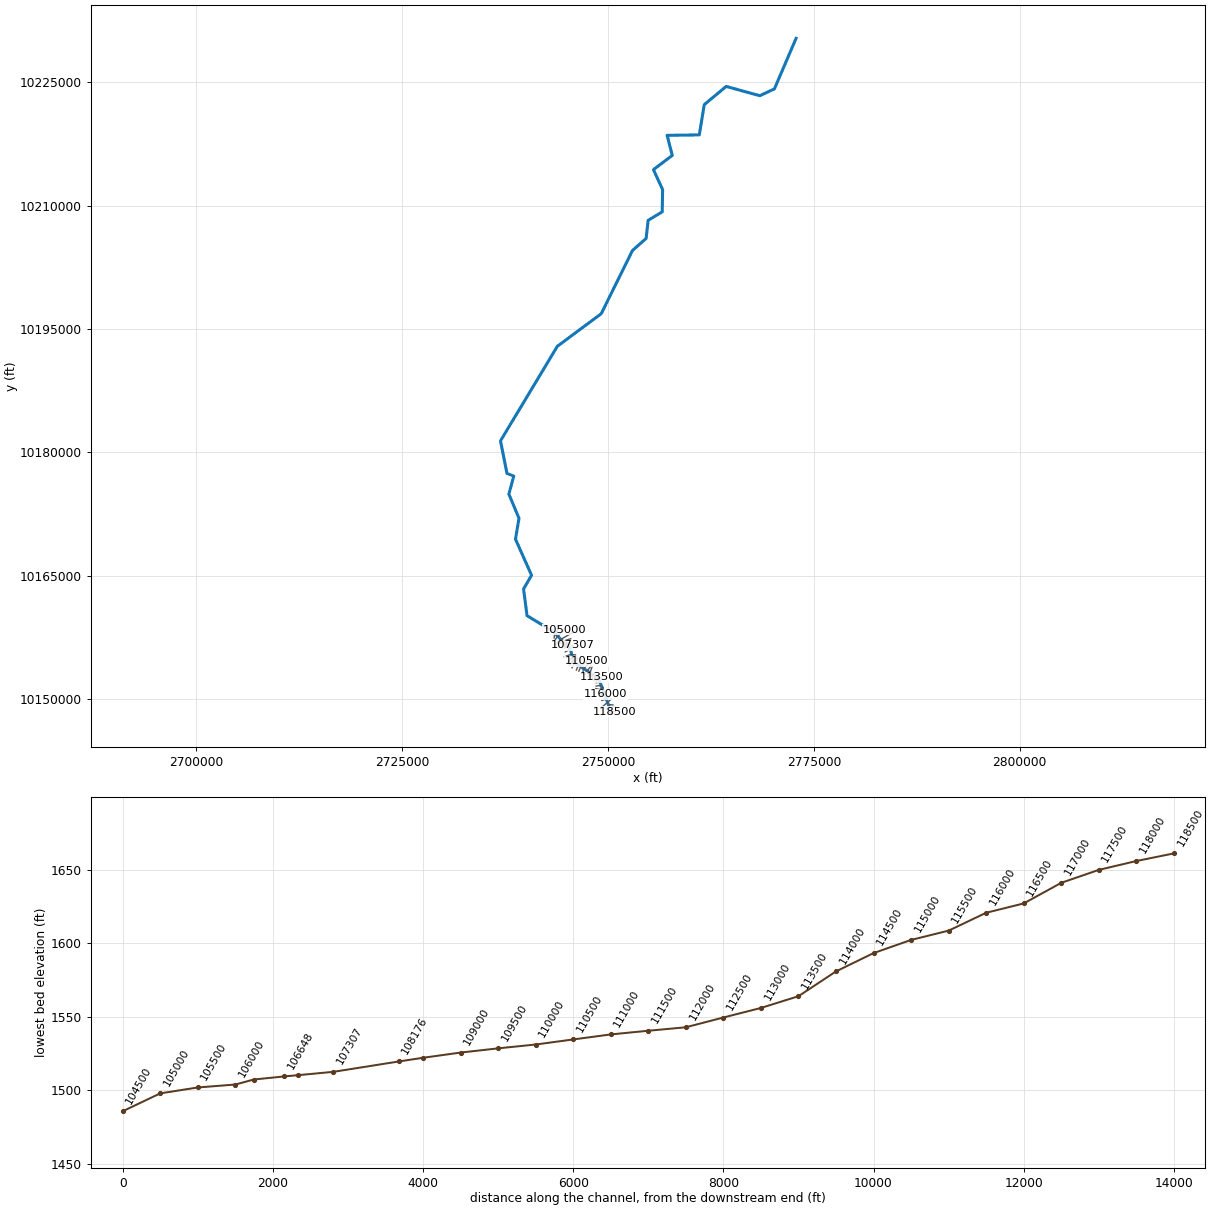
--- HICKORY CREEK.prj (project) ---

Proj Title=HICKORY CREEK Base Level Engineering
Current Plan=p01
Default Exp/Contr=0.3,0.1
English Units
Geom File=g01
Flow File=f01
Plan File=p01
Y Axis Title=Elevation
X Axis Title(PF)=Main Channel Distance
X Axis Title(XS)=Station
BEGIN DESCRIPTION:
HICKORY CREEK
END DESCRIPTION:
DSS Export Rating Curves= 0
DSS Export Rating Curve Sorted= 0
DSS Export Volume Flow Curves= 0
DXF OffsetX= 0
DXF OffsetY= 0
DXF ScaleX= 1
DXF ScaleY= 10

--- HICKORY CREEK.p01 (plan) ---

Plan Title=Multiple Run
Short Identifier=Multiple
Geom File=g01
Flow File=f01
Subcritical Flow
K Sum by GR= 0
Std Step Tol= 0.01
Critical Tol= 0.01
Num of Std Step Trials= 20
Max Error Tol= 0.3
Flow Tol Ratio= 0.001
Split Flow NTrial= 30
Split Flow Tol= 0.02
Split Flow Ratio= 0.02
Log Output Level= 0
Friction Slope Method= 1
Unsteady Friction Slope Method= 2
Unsteady Bridges Friction Slope Method= 1
Parabolic Critical Depth
Global Vel Dist=  1 , 1 , 1
Global Log Level= 0
CheckData=True
Encroach Param= -1, 0, 0, 0
BEGIN DESCRIPTION:
Multiple Run
END DESCRIPTION:

--- HICKORY CREEK.f01 (steady flow) ---

Flow Title=Multiple
Program Version=4.10
Number of Profiles= 7
Profile Names=10-year,25-year,50-year,1pct_min,100-year,1pct_plu,500-year
River Rch & RM=HICKORY CREEK,Reach-1         ,118500
     320     502     834     725    1121    1733    1562
River Rch & RM=HICKORY CREEK,Reach-1         ,115000
     437     704    1207     971    1651    2805    2323
River Rch & RM=HICKORY CREEK,Reach-1         ,111500
     815    1360    2429    1908    3384    6001    4711
River Rch & RM=HICKORY CREEK,Reach-1         ,107307
     961    1623    2868    2201    4013    7315    5577
River Rch & RM=HICKORY CREEK,Reach-1         ,105500
    2031    3637    7058    5511   10166   18752   14008
River Rch & RM=HICKORY CREEK,Reach-1         ,101000
    2396    4351    8012    5951   11553   22428   15868
River Rch & RM=HICKORY CREEK,Reach-1         ,95000
    4361    8200   14193   10321   20490   40679   27610
River Rch & RM=HICKORY CREEK,Reach-1         ,89500
    4387    8255   14227   10174   20553   41521   27715
River Rch & RM=HICKORY CREEK,Reach-1         ,86500
    4594    8656   14838   10538   21434   43593   28867
River Rch & RM=HICKORY CREEK,Reach-1         ,84872
   14815   27880   44233   32395   62868  122004   81998
River Rch & RM=HICKORY CREEK,Reach-1         ,84000
   18619   34803   54191   39419   76606  148872   99229
River Rch & RM=HICKORY CREEK,Reach-1         ,79000
   18851   35226   54839   39894   77520  150635  100407
River Rch & RM=HICKORY CREEK,Reach-1         ,77000
   18229   34053   52994   38684   74917  145087   97035
River Rch & RM=HICKORY CREEK,Reach-1         ,74000
   49342   89675  132161   91852  183027  364704  231899
River Rch & RM=HICKORY CREEK,Reach-1         ,69500
   46128   83760  123268   86018  170624  338448  216076
River Rch & RM=HICKORY CREEK,Reach-1         ,65500
   45824   83176  122363   85420  169339  335700  214406
River Rch & RM=HICKORY CREEK,Reach-1         ,65000
   43441   78842  115946   81194  160449  317065  203138
River Rch & RM=HICKORY CREEK,Reach-1         ,62000
   39381   71395  104845   73847  145006  284735  183486
River Rch & RM=HICKORY CREEK,Reach-1         ,56500
   37918   68736  100915   71239  139564  273421  176591
River Rch & RM=HICKORY CREEK,Reach-1         ,54500
   36783   66537   97489   68950  134683  263084  170234
River Rch & RM=HICKORY CREEK,Reach-1         ,50000
   36390   65757   96250   68120  132902  259292  167895
River Rch & RM=HICKORY CREEK,Reach-1         ,47500
   34439   62223   91043   64647  125702  244420  158788
River Rch & RM=HICKORY CREEK,Reach-1         ,44000
   34247   61836   90423   64231  124808  242515  157607
River Rch & RM=HICKORY CREEK,Reach-1         ,42000
   32884   59330   86684   61727  119600  231733  150973
River Rch & RM=HICKORY CREEK,Reach-1         ,38000
   31650   57086   83369   59504  115009  222286  145156
River Rch & RM=HICKORY CREEK,Reach-1         ,32500
   31027   55944   81669   58362  112645  217416  142149
River Rch & RM=HICKORY CREEK,Reach-1         ,30500
   29609   53375   77885   55818  107414  206705  135532
River Rch & RM=HICKORY CREEK,Reach-1         ,26500
   28434   51241   74737   53695  103056  197795  130013
River Rch & RM=HICKORY CREEK,Reach-1         ,21500
   26661   48029   70011   50500   96524  184495  121753
River Rch & RM=HICKORY CREEK,Reach-1         ,14500
   25770   46422   67653   48901   93270  177893  117643
River Rch & RM=HICKORY CREEK,Reach-1         ,11000
   31694   56614   81970   58527  112532  216369  141343
River Rch & RM=HICKORY CREEK,Reach-1         ,7000
   33416   59459   85815   61087  117584  226334  147403
Boundary for River Rch & Prof#=HICKORY CREEK,Reach-1         , 1
Up Type= 0
Dn Type= 3
Dn Slope=0.0025
Boundary for River Rch & Prof#=HICKORY CREEK,Reach-1         , 2
Up Type= 0
Dn Type= 3
Dn Slope=0.0025
Boundary for River Rch & Prof#=HICKORY CREEK,Reach-1         , 3
Up Type= 0
Dn Type= 3
Dn Slope=0.0025
Boundary for River Rch & Prof#=HICKORY CREEK,Reach-1         , 4
Up Type= 0
Dn Type= 3
Dn Slope=0.0025
Boundary for River Rch & Prof#=HICKORY CREEK,Reach-1         , 5
Up Type= 0
Dn Type= 3
Dn Slope=0.0025
Boundary for River Rch & Prof#=HICKORY CREEK,Reach-1         , 6
Up Type= 0
Dn Type= 3
Dn Slope=0.0025
Boundary for River Rch & Prof#=HICKORY CREEK,Reach-1         , 7
Up Type= 0
Dn Type= 3
Dn Slope=0.0025
DSS Import GetInterval= 0
DSS Import GetPeak= 0
DSS Import FillOption= 0

--- HICKORY CREEK.g01 (geometry) ---

Geom Title=Existing Conditions
Program Version=4.10

River Reach=HICKORY CREEK   ,Reach-1
Reach XY= 30
      2750443.75       10148286.      2748851.75       10152540.
      2745751.75       10154591.      2745453.75       10156087.
      2743328.75       10158229.       2740162.5       10160169.
      2739739.25       10163419.      2740713.75       10165069.
       2738761.5       10169457.       2739186.5       10172002.
      2737956.25       10174941.      2738553.75       10177132.
       2737727.5       10177449.        2736941.       10181417.
       2743842.5       10192906.       2749175.5       10196869.
      2752968.25       10204552.       2754621.5       10206011.
       2754873.5       10208221.        2756581.       10209249.
      2756627.75       10211961.      2755513.25       10214378.
      2757801.75       10216108.      2757174.75       10218550.
        2761084.       10218604.        2761684.       10222281.
       2764346.5       10224494.       2768436.5       10223369.
      2770204.75       10224196.      2772837.25     10230341.39

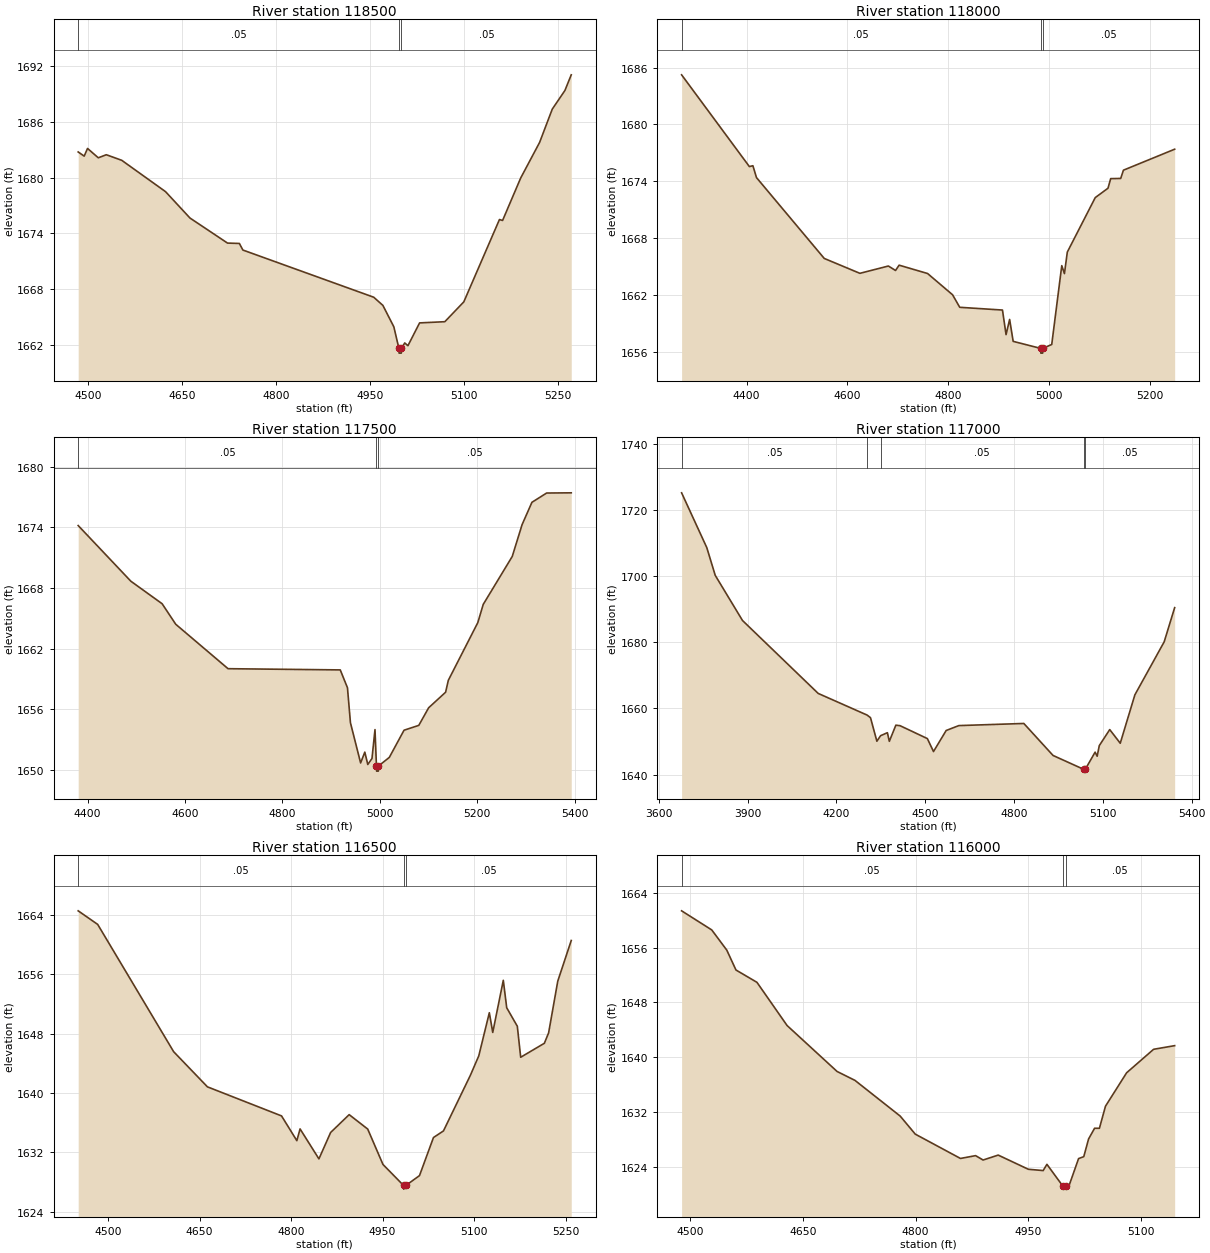
Type RM Length L Ch R = 1 ,118500  ,500,500,500
BEGIN DESCRIPTION:
HICKORY CREEK 237.0
END DESCRIPTION:
XS GIS Cut Line= 3
      2750005.71     10148353.12      2750486.39     10148539.11
      2750755.69     10148503.11
#Sta/Elev= 30
  4484.6 1682.77  4494.2 1682.32  4499.5 1683.15  4516.7 1682.14  4529.5 1682.47
  4554.1 1681.87    4624 1678.49  4663.1 1675.64    4723 1672.94  4741.9  1672.9
  4747.5 1672.19  4956.4  1667.1    4971 1666.22  4988.5 1663.91  4996.6 1661.57
  4996.9 1661.07  5000.4 1661.07  5000.6 1661.57  5005.9 1662.17    5011 1661.87
  5029.6 1664.33  5069.9 1664.46  5100.2  1666.6  5157.1 1675.48  5162.1 1675.38
    5191 1679.96  5221.2  1683.8  5241.4 1687.39  5261.6  1689.4  5271.7 1691.09
#Mann= 3 ,-1 , 0
  4484.6     .05       0  4996.6     .05       0  5000.6     .05       0
Bank Sta=4996.6,5000.6
XS Rating Curve= 0 ,0
Exp/Cntr=0.3,0.1

Type RM Length L Ch R = 1 ,118000  ,500,500,500
BEGIN DESCRIPTION:
HICKORY CREEK 236.0
END DESCRIPTION:
XS GIS Cut Line= 3
      2750005.67     10148503.09      2750521.66     10149017.78
      2750755.69     10149103.11
#Sta/Elev= 30
  4271.2 1685.23  4405.6 1675.56  4412.6 1675.65  4419.7  1674.4  4554.1 1665.88
  4624.8 1664.31  4681.3 1665.08  4695.5 1664.61  4702.6 1665.17  4759.1 1664.29
  4808.6 1662.05  4822.8 1660.73  4907.6 1660.44  4914.7 1657.85  4921.8 1659.45
  4928.8 1657.14  4983.4  1656.4  4983.7  1655.9  4987.2  1655.9  4987.4  1656.4
  5005.3 1656.81  5025.2 1665.12  5030.5 1664.28  5036.2 1666.55  5091.6 1672.29
  5116.9 1673.28  5122.2 1674.29  5142.1 1674.31  5147.5 1675.18  5249.1 1677.39
#Mann= 3 ,-1 , 0
  4271.2     .05       0  4983.4     .05       0  4987.4     .05       0
Bank Sta=4983.4,4987.4
XS Rating Curve= 0 ,0
Exp/Cntr=0.3,0.1

Type RM Length L Ch R = 1 ,117500  ,500,500,500
BEGIN DESCRIPTION:
HICKORY CREEK 235.0
END DESCRIPTION:
XS GIS Cut Line= 3
      2749855.68      10148853.1       2750216.5      10149356.3
      2750605.68     10149303.11
#Sta/Elev= 30
  4380.8 1674.18  4488.9 1668.67  4553.1 1666.44    4581 1664.41  4688.4 1660.01
  4918.7 1659.89  4933.5 1658.12  4939.6 1654.66  4960.5 1650.68  4969.1 1651.75
  4975.2 1650.53  4983.8 1651.12    4990 1653.98    4993 1650.37  4993.3 1649.87
  4996.8 1649.87    4997 1650.37  5019.4 1651.23  5049.6 1653.92  5079.9  1654.4
  5100.1 1656.14  5134.9 1657.68  5140.5 1658.86    5201 1664.57  5212.2 1666.38
  5271.7 1671.12  5291.9 1674.27  5312.1 1676.48  5342.3  1677.4  5392.8 1677.42
#Mann= 3 ,-1 , 0
  4380.8     .05       0    4993     .03       0    4997     .05       0
Bank Sta=4993,4997
XS Rating Curve= 0 ,0
Exp/Cntr=0.3,0.1

Type RM Length L Ch R = 1 ,117000  ,500,500,500
BEGIN DESCRIPTION:
HICKORY CREEK 234.0
END DESCRIPTION:
XS GIS Cut Line= 3
      2749155.67      10148953.1      2750158.57     10149815.81
      2750405.68     10150053.11
#Sta/Elev= 30
  3677.1 1725.11  3762.2 1708.56  3790.7 1700.19  3882.8 1686.56  4138.5 1664.54
  4303.8    1658  4315.2 1657.21  4336.7 1650.11  4349.3 1651.78  4372.2 1652.68
  4378.8 1650.08  4400.8 1654.95    4415  1654.8  4507.2 1650.91    4528 1646.99
  4570.8 1653.35  4613.6 1654.83  4833.1 1655.47  4931.8 1645.81  5036.4 1641.58
  5036.6 1641.08  5040.4 1641.58  5073.9 1646.81  5080.8 1645.58    5088 1648.78
  5123.3 1653.62  5158.8  1649.5  5208.2 1664.11  5307.2 1680.12  5342.6 1690.44
#Mann= 5 ,-1 , 0
  3677.1     .05       0  4303.8     .12       0  4349.3     .05       0
  5036.4     .05       0  5040.4     .05       0
Bank Sta=5036.4,5040.4
XS Rating Curve= 0 ,0
Exp/Cntr=0.3,0.1

Type RM Length L Ch R = 1 ,116500  ,500,500,500
BEGIN DESCRIPTION:
HICKORY CREEK 233.0
END DESCRIPTION:
XS GIS Cut Line= 3
      2749255.64     10149853.09      2749770.49     10150043.97
       2750005.7     10150153.12
#Sta/Elev= 30
  4450.9 1664.51  4482.9 1662.68  4607.4 1645.56  4662.8 1640.83  4784.3 1636.92
  4809.4 1633.59  4814.7 1635.17  4845.6 1631.14  4864.8 1634.69  4895.2 1637.09
  4925.6 1635.15  4950.6 1630.39  4984.3 1627.57  4984.6 1627.07  4988.3 1627.57
  5010.5 1628.89  5033.4 1634.01  5049.8  1634.9  5093.9 1642.38  5107.7    1645
    5125  1650.8  5130.6 1648.15  5147.9 1655.16  5153.5 1651.47  5170.9 1648.98
  5176.4 1644.81  5215.2 1646.69  5222.2 1648.09  5237.2 1655.05  5259.3 1660.52
#Mann= 3 ,-1 , 0
  4450.9     .05       0  4984.3     .05       0  4988.3     .05       0
Bank Sta=4984.3,4988.3
XS Rating Curve= 0 ,0
Exp/Cntr=0.3,0.1

Type RM Length L Ch R = 1 ,116000  ,500,500,500
BEGIN DESCRIPTION:
HICKORY CREEK 232.0
END DESCRIPTION:
XS GIS Cut Line= 3
      2749105.71     10150453.11      2749615.58     10150489.96
      2749705.66     10150603.08
#Sta/Elev= 30
  4488.8 1661.38  4528.9 1658.59  4548.9 1655.64  4561.1 1652.74    4589 1650.94
  4629.1 1644.63  4695.6 1637.92  4719.4 1636.62  4779.5 1631.41  4799.6 1628.77
  4859.7 1625.22  4879.8 1625.63  4889.8 1624.99  4909.9 1625.71    4950 1623.64
  4969.7 1623.45  4974.7 1624.36  4995.5 1621.24  4995.8 1620.74  4999.5 1621.24
  5004.1 1621.24  5016.8  1625.2  5023.7 1625.48  5030.1 1628.06  5038.1 1629.63
  5044.5 1629.62  5052.6 1632.85  5080.7 1637.73  5116.6 1641.16  5144.6 1641.69
#Mann= 3 ,-1 , 0
  4488.8     .05       0  4995.5     .03       0  4999.5     .05       0
Bank Sta=4995.5,4999.5
XS Rating Curve= 0 ,0
Exp/Cntr=0.3,0.1

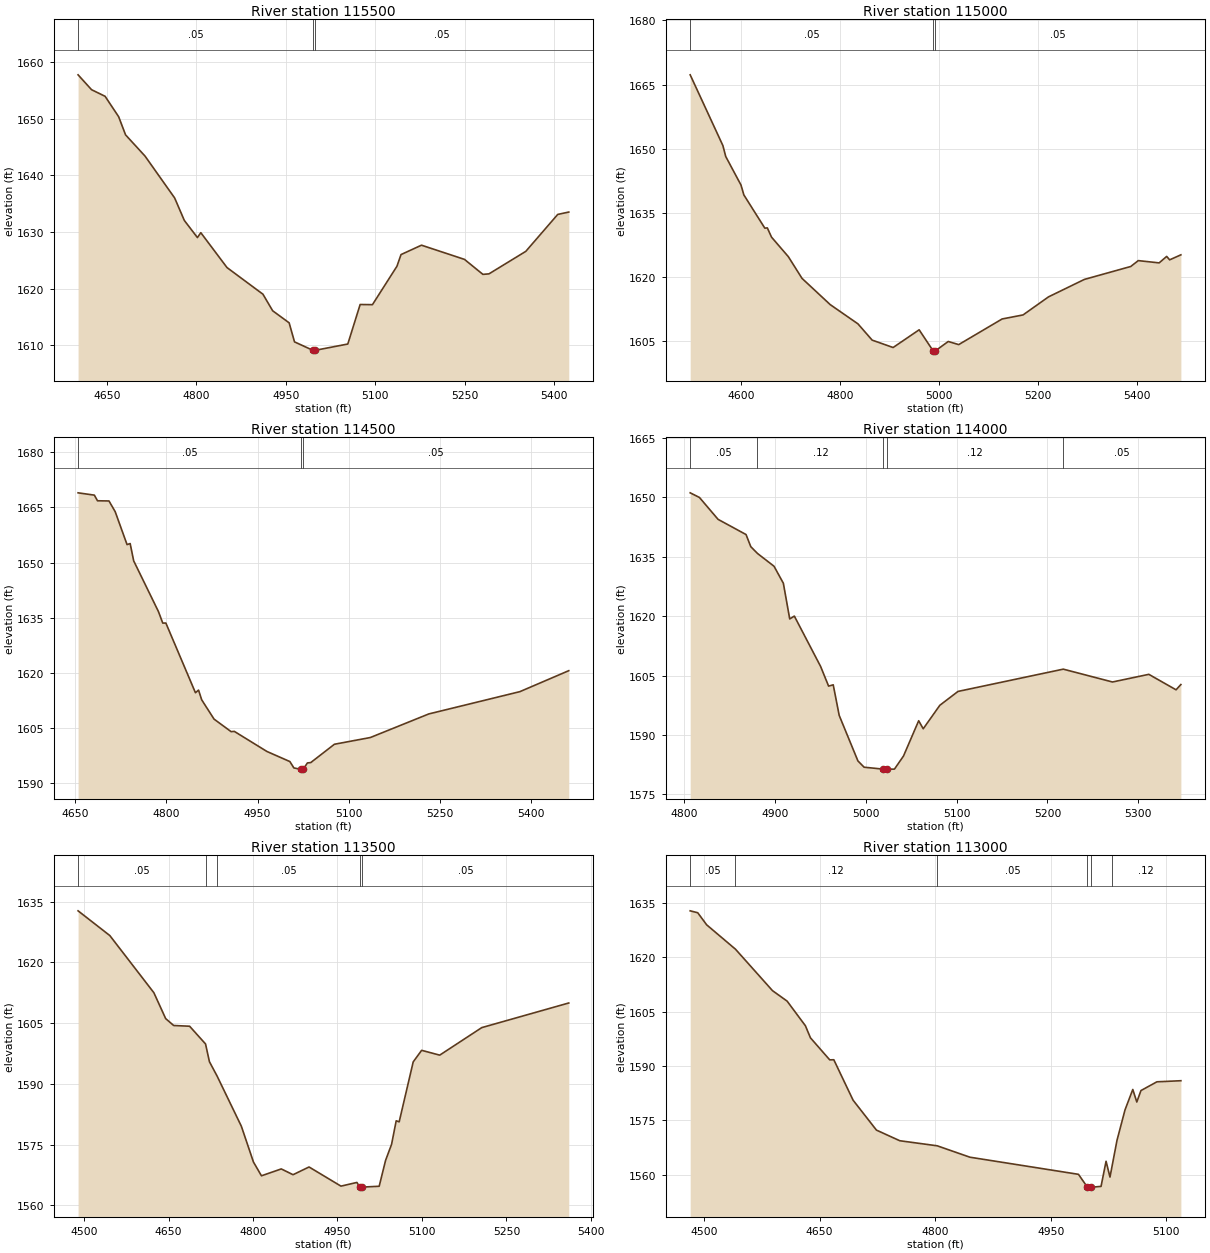
Type RM Length L Ch R = 1 ,115500  ,500,500,500
BEGIN DESCRIPTION:
HICKORY CREEK 231.0
END DESCRIPTION:
XS GIS Cut Line= 3
       2749105.7     10150503.15      2749293.22     10150854.43
      2749705.68     10150953.11
#Sta/Elev= 30
  4601.8  1657.8  4624.4 1655.17  4647.1    1654  4669.8 1650.39  4681.4 1647.18
    4714 1643.43  4763.6 1636.03  4779.9 1632.04  4801.8 1629.02  4807.5 1629.88
  4851.4 1623.71  4911.6    1619  4927.9 1616.07  4955.5 1613.94  4964.5 1610.57
  4995.3 1609.08  4995.6 1608.58  4999.3 1609.08  5053.8 1610.19  5074.5 1617.18
  5095.1 1617.15  5136.2 1623.95    5143 1626.01  5177.3 1627.67  5249.3 1625.16
  5280.2 1622.51  5290.4  1622.6  5352.1 1626.58  5405.6 1633.11  5424.1 1633.53
#Mann= 3 ,-1 , 0
  4601.8     .05       0  4995.3     .05       0  4999.3     .05       0
Bank Sta=4995.3,4999.3
XS Rating Curve= 0 ,0
Exp/Cntr=0.3,0.1

Type RM Length L Ch R = 1 ,115000  ,500,500,500
BEGIN DESCRIPTION:
HICKORY CREEK 230.0
END DESCRIPTION:
XS GIS Cut Line= 3
       2748505.7     10151303.11      2748995.11     10151187.85
      2749405.68     10151453.11
#Sta/Elev= 30
  4497.2 1667.29  4563.3 1650.76  4569.1  1648.2  4599.9 1641.54  4605.7 1639.23
    4648 1631.48  4653.1 1631.53  4661.6 1629.37  4695.5 1624.82  4723.2 1619.74
  4780.2 1613.61  4836.2 1609.12  4864.9 1605.32  4907.3 1603.59  4959.9 1607.73
  4988.3 1602.78  4988.6 1602.28  4992.3 1602.78  5018.7    1605  5039.8 1604.27
  5127.6 1610.26  5169.8  1611.2  5221.3 1615.42  5293.8  1619.5  5387.5 1622.52
  5402.7 1623.89  5444.9 1623.36  5460.1 1624.87  5466.1 1624.07  5488.8 1625.24
#Mann= 3 ,-1 , 0
  4497.2     .05       0  4988.3     .05       0  4992.3     .05       0
Bank Sta=4988.3,4992.3
XS Rating Curve= 0 ,0
Exp/Cntr=0.3,0.1

Type RM Length L Ch R = 1 ,114500  ,500,500,500
BEGIN DESCRIPTION:
HICKORY CREEK 229.0
END DESCRIPTION:
XS GIS Cut Line= 3
      2748555.69     10151603.11      2748895.35     10151664.17
      2749305.65     10151453.13
#Sta/Elev= 30
  4654.9 1668.93  4681.7  1668.3  4686.8 1666.77  4705.7 1666.72  4715.9 1663.81
  4735.4 1654.87  4740.5 1655.15  4746.3 1650.45    4787 1636.67  4794.1 1633.54
  4799.2 1633.55  4847.8 1614.62  4852.9 1615.33  4858.1 1612.69  4878.4 1607.45
  4906.5 1604.04  4911.6 1604.13  4965.3 1598.66    5003 1595.92  5009.6 1594.19
  5020.8 1593.82  5021.1 1593.32    5025 1593.82  5031.8 1595.54  5037.4 1595.65
  5076.2 1600.62  5135.3 1602.45  5231.4 1608.86    5381 1614.91  5461.4 1620.61
#Mann= 3 ,-1 , 0
  4654.9     .05       0  5020.8     .05       0    5025     .05       0
Bank Sta=5020.8,5025
XS Rating Curve= 0 ,0
Exp/Cntr=0.3,0.1

Type RM Length L Ch R = 1 ,114000  ,500,500,500
BEGIN DESCRIPTION:
HICKORY CREEK 228.0
END DESCRIPTION:
XS GIS Cut Line= 3
      2748555.73     10152003.12       2748744.1     10152046.48
      2749090.97     10152055.93
#Sta/Elev= 30
  4806.7 1651.08  4816.9 1649.91  4837.4 1644.39  4868.2 1640.56  4873.4 1637.51
  4880.8 1635.79    4899 1632.57  4909.3 1628.27  4916.3 1619.27  4921.4 1619.99
  4950.3  1607.3  4959.1 1602.33  4964.2 1602.66  4970.8 1594.93  4991.4 1583.46
  4998.2 1581.88  5019.4 1581.39  5019.7 1580.89  5023.8 1581.39  5031.6 1581.39
  5041.6 1584.71  5058.3  1593.6  5063.3 1591.57  5081.6  1597.5  5101.6 1600.99
  5217.5 1606.61  5271.7 1603.37  5311.7  1605.3  5341.7  1601.4    5347 1602.73
#Mann= 5 ,-1 , 0
  4806.7     .05       0  4880.8     .12       0  5019.4     .07       0
  5023.8     .12       0  5217.5     .05       0
Bank Sta=5019.4,5023.8
XS Rating Curve= 0 ,0
Exp/Cntr=0.3,0.1

Type RM Length L Ch R = 1 ,113500  ,500,500,500
BEGIN DESCRIPTION:
HICKORY CREEK 227.0
END DESCRIPTION:
XS GIS Cut Line= 3
      2748505.71     10152153.13      2748852.52     10152528.01
      2749190.28     10152654.88
#Sta/Elev= 30
  4489.3 1632.76  4545.7 1626.65  4623.9 1612.54  4644.9 1606.14  4659.1 1604.44
  4687.4 1604.26  4715.7 1599.88  4722.6  1595.5  4736.3 1591.93  4779.3 1579.56
  4800.8 1570.72    4815 1567.32  4850.2 1569.02  4871.1 1567.59  4899.5  1569.5
  4956.2 1564.77  4984.5 1565.68  4989.7 1564.53    4990 1564.03  4994.1 1564.53
  5024.1 1564.74  5035.4 1571.11  5046.1  1575.1  5054.3  1580.9  5059.6 1580.65
  5084.5 1595.45  5099.5 1598.31  5131.6 1597.12  5206.3 1603.92  5360.8    1610
#Mann= 5 ,-1 , 0
  4489.3     .05       0  4715.7     .12       0  4736.3     .05       0
  4989.7     .05       0  4994.1     .05       0
Bank Sta=4989.7,4994.1
XS Rating Curve= 0 ,0
Exp/Cntr=0.3,0.1

Type RM Length L Ch R = 1 ,113000  ,500,500,500
BEGIN DESCRIPTION:
HICKORY CREEK 226.0
END DESCRIPTION:
XS GIS Cut Line= 3
      2748305.68     10152303.09      2748486.69     10152788.32
      2748455.69     10152903.11
#Sta/Elev= 30
  4482.1 1632.76  4491.9 1632.23  4503.5  1628.9  4540.9 1622.18  4588.9 1610.76
  4607.9 1607.87  4631.6 1601.09  4638.2 1597.75  4663.2 1591.68  4668.5 1591.71
  4693.5 1580.57  4723.8 1572.32  4754.1 1569.39  4802.7 1567.99  4845.1 1564.85
    4986 1560.13  4997.7 1556.55    4998 1556.05  5002.1 1556.55  5015.3 1556.81
  5021.8 1563.73  5026.9 1559.37    5029 1561.71    5036  1569.5  5046.4 1577.89
  5056.5 1583.52  5061.7 1580.06  5067.1 1583.22  5087.8 1585.63  5118.9 1585.93
#Mann= 6 ,-1 , 0
  4482.1     .05       0  4540.9     .12       0  4802.7     .05       0
  4997.7     .05       0  5002.1     .05       0    5029     .12       0
Bank Sta=4997.7,5002.1
XS Rating Curve= 0 ,0
Exp/Cntr=0.3,0.1

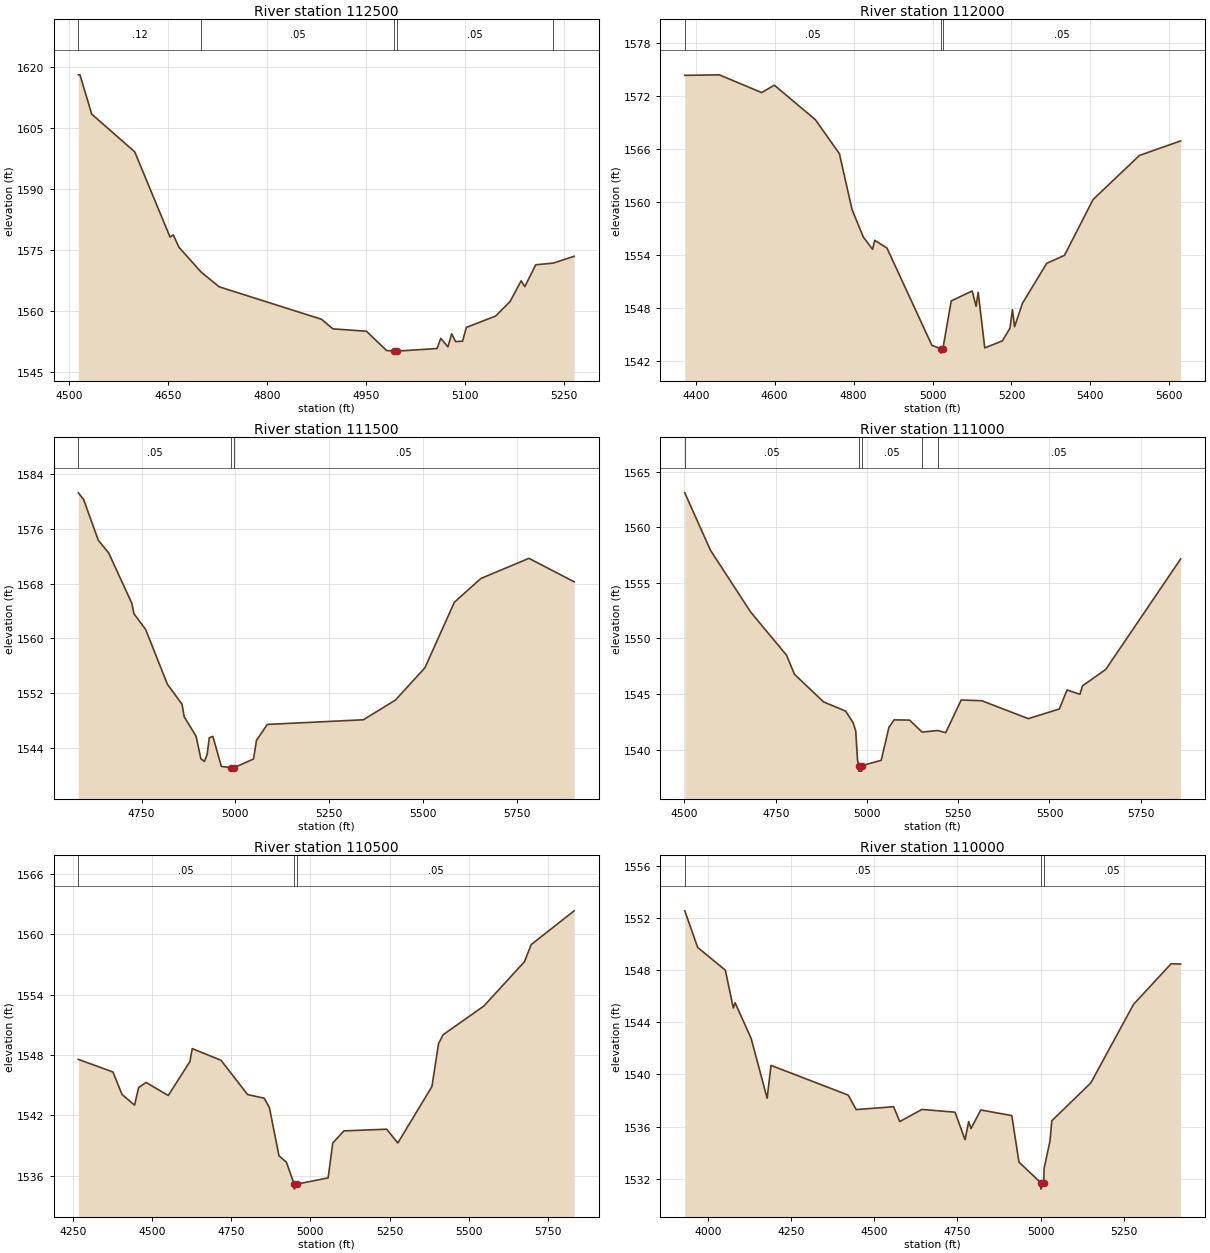
Type RM Length L Ch R = 1 ,112500  ,500,500,500
BEGIN DESCRIPTION:
HICKORY CREEK 225.0
END DESCRIPTION:
XS GIS Cut Line= 3
      2748105.68     10152453.12      2748019.44     10152931.71
      2748255.67     10153053.11
#Sta/Elev= 30
  4513.7    1618  4516.2    1618    4534 1608.33  4599.2 1599.07  4652.8  1578.1
  4657.8 1578.64  4666.1 1575.62  4700.3 1569.44  4727.1 1565.88  4882.4 1557.89
  4899.8 1555.53  4950.6 1554.94  4981.1 1550.21  4992.4 1550.06  4992.8 1549.56
  4996.9 1550.06  5057.7 1550.69  5063.3 1553.19  5074.2  1551.1  5079.9 1554.31
  5085.7 1552.41  5096.4  1552.5  5102.1 1555.88  5146.4 1558.67  5168.6 1562.28
  5185.2 1567.35  5190.8 1565.91  5207.3 1571.29    5234  1571.7  5265.6 1573.38
#Mann= 5 ,-1 , 0
  4513.7     .12       0  4700.3     .05       0  4992.4     .05       0
  4996.9     .05       0    5234     .12       0
Bank Sta=4992.4,4996.9
XS Rating Curve= 0 ,0
Exp/Cntr=0.3,0.1

Type RM Length L Ch R = 1 ,112000  ,500,500,500
BEGIN DESCRIPTION:
HICKORY CREEK 224.0
END DESCRIPTION:
XS GIS Cut Line= 3
      2747596.58     10152785.13      2747851.72     10153358.53
      2748064.67     10153949.96
#Sta/Elev= 30
  4372.4 1574.35  4459.8 1574.41  4567.2  1572.4  4599.2 1573.24  4703.1 1569.34
  4764.2 1565.48  4796.1 1559.16  4824.8 1556.05  4848.1 1554.67  4853.6 1555.69
  4884.6 1554.81  4998.5  1543.8    5021 1543.42  5021.4 1542.92  5026.3 1543.42
  5047.4 1548.83  5100.5 1549.95  5110.4 1548.23  5115.7  1549.8  5132.4 1543.51
  5177.1 1544.31  5196.2 1545.74  5202.5 1547.83  5207.9 1545.91  5227.9 1548.56
  5289.3 1553.08  5334.3 1553.98  5406.8  1560.3  5524.3 1565.29  5628.6 1566.93
#Mann= 3 ,-1 , 0
  4372.4     .05       0    5021     .03       0  5026.3     .05       0
Bank Sta=5021,5026.3
XS Rating Curve= 0 ,0
Exp/Cntr=0.3,0.1

Type RM Length L Ch R = 1 ,111500  ,500,500,500
BEGIN DESCRIPTION:
HICKORY CREEK 223.0
END DESCRIPTION:
XS GIS Cut Line= 3
      2747205.67     10153003.08      2747393.68     10153376.63
      2747955.93     10154081.96
#Sta/Elev= 30
  4581.8 1581.27  4595.8 1580.31  4634.8 1574.35  4662.7 1572.46  4724.1 1565.14
  4729.7 1563.61    4761 1561.29    4819 1553.27    4858 1550.35  4863.6 1548.53
  4895.3 1545.67  4908.2 1542.36  4917.7 1541.99  4924.9 1543.03  4930.5 1545.46
  4940.1 1545.65  4962.5 1541.27  4987.7 1541.07  4988.2 1540.57    4996 1541.07
  5048.2 1542.34  5056.2 1545.07    5085  1547.4  5340.8 1548.08  5426.1 1550.96
  5504.6 1555.68  5583.1 1565.27  5653.5 1568.74  5781.6 1571.69    5902 1568.26
#Mann= 3 ,-1 , 0
  4581.8     .05       0  4987.7     .05       0    4996     .05       0
Bank Sta=4987.7,4996
XS Rating Curve= 0 ,0
Exp/Cntr=0.3,0.1

Type RM Length L Ch R = 1 ,111000  ,500,500,500
BEGIN DESCRIPTION:
HICKORY CREEK 222.0
END DESCRIPTION:
XS GIS Cut Line= 3
      2746955.69     10153153.13      2746982.19     10153651.53
      2747580.15     10154268.66
#Sta/Elev= 30
  4500.9 1563.09    4571 1557.94  4681.1 1552.38  4779.8 1548.48  4801.3 1546.77
  4881.4 1544.28  4941.5 1543.46  4961.5 1542.44  4969.1  1541.7  4974.1 1539.08
  4977.1 1538.56  4977.6 1538.06  4985.5 1538.06    4986 1538.56    5039 1539.03
  5060.1 1541.99  5074.2 1542.67  5116.7 1542.65    5151 1541.57    5194 1541.71
  5215.7 1541.52  5258.2 1544.46  5314.7 1544.39  5442.1 1542.78    5527 1543.65
  5548.1 1545.36  5583.5 1544.97  5590.5 1545.73  5654.3 1547.21  5859.3 1557.14
#Mann= 5 ,-1 , 0
  4500.9     .05       0  4977.1     .05       0    4986     .05       0
    5151     .12       0    5194     .05       0
Bank Sta=4977.1,4986
XS Rating Curve= 0 ,0
Exp/Cntr=0.3,0.1

Type RM Length L Ch R = 1 ,110500  ,500,500,500
BEGIN DESCRIPTION:
HICKORY CREEK 221.0
END DESCRIPTION:
XS GIS Cut Line= 3
      2746455.95     10153420.53      2746749.15     10154091.46
      2747405.72     10154603.14
#Sta/Elev= 30
  4267.8 1547.55  4376.9  1546.3  4405.8 1544.06  4445.2    1543    4458 1544.74
  4481.4 1545.26  4551.6 1543.96  4619.8 1547.33  4627.3 1548.62  4718.1 1547.46
    4802 1544.05  4854.2 1543.69  4870.8 1542.75    4901 1537.96  4924.4 1537.33
  4948.8 1535.15  4949.3 1534.65  4957.7 1535.15  5056.1 1535.77  5070.6 1539.23
  5105.9 1540.44  5240.7 1540.61    5276 1539.24  5383.6 1544.85  5404.4 1549.11
  5418.9    1550  5547.4 1552.85  5675.8 1557.27  5696.7 1558.96  5832.4 1562.32
#Mann= 3 ,-1 , 0
  4267.8     .05       0  4948.8     .03       0  4957.7     .05       0
Bank Sta=4948.8,4957.7
XS Rating Curve= 0 ,0
Exp/Cntr=0.3,0.1

Type RM Length L Ch R = 1 ,110000  ,500,500,500
BEGIN DESCRIPTION:
HICKORY CREEK 220.0
END DESCRIPTION:
XS GIS Cut Line= 3
      2746155.68      10153553.1      2746558.84     10154543.16
      2746726.15     10154929.49
#Sta/Elev= 30
    3931 1552.55  3969.8 1549.74  4052.8    1548  4076.8  1545.1  4082.2  1545.5
  4130.3 1542.77  4178.4 1538.18  4190.1  1540.7  4421.9 1538.42    4446 1537.31
  4558.4 1537.53    4577 1536.39  4643.6 1537.32    4743 1537.11  4773.2    1535
    4784 1536.39  4791.1 1535.86  4820.5 1537.28  4913.6 1536.85  4935.2 1533.28
  5000.5 1531.71    5001 1531.21  5009.5 1531.71  5010.8  1532.8  5028.5 1534.92
  5033.9 1536.45  5151.3 1539.36  5279.6 1545.38  5392.3 1548.49    5421 1548.47
#Mann= 3 ,-1 , 0
    3931     .05       0  5000.5     .03       0  5009.5     .05       0
Bank Sta=5000.5,5009.5
XS Rating Curve= 0 ,0
Exp/Cntr=0.3,0.1

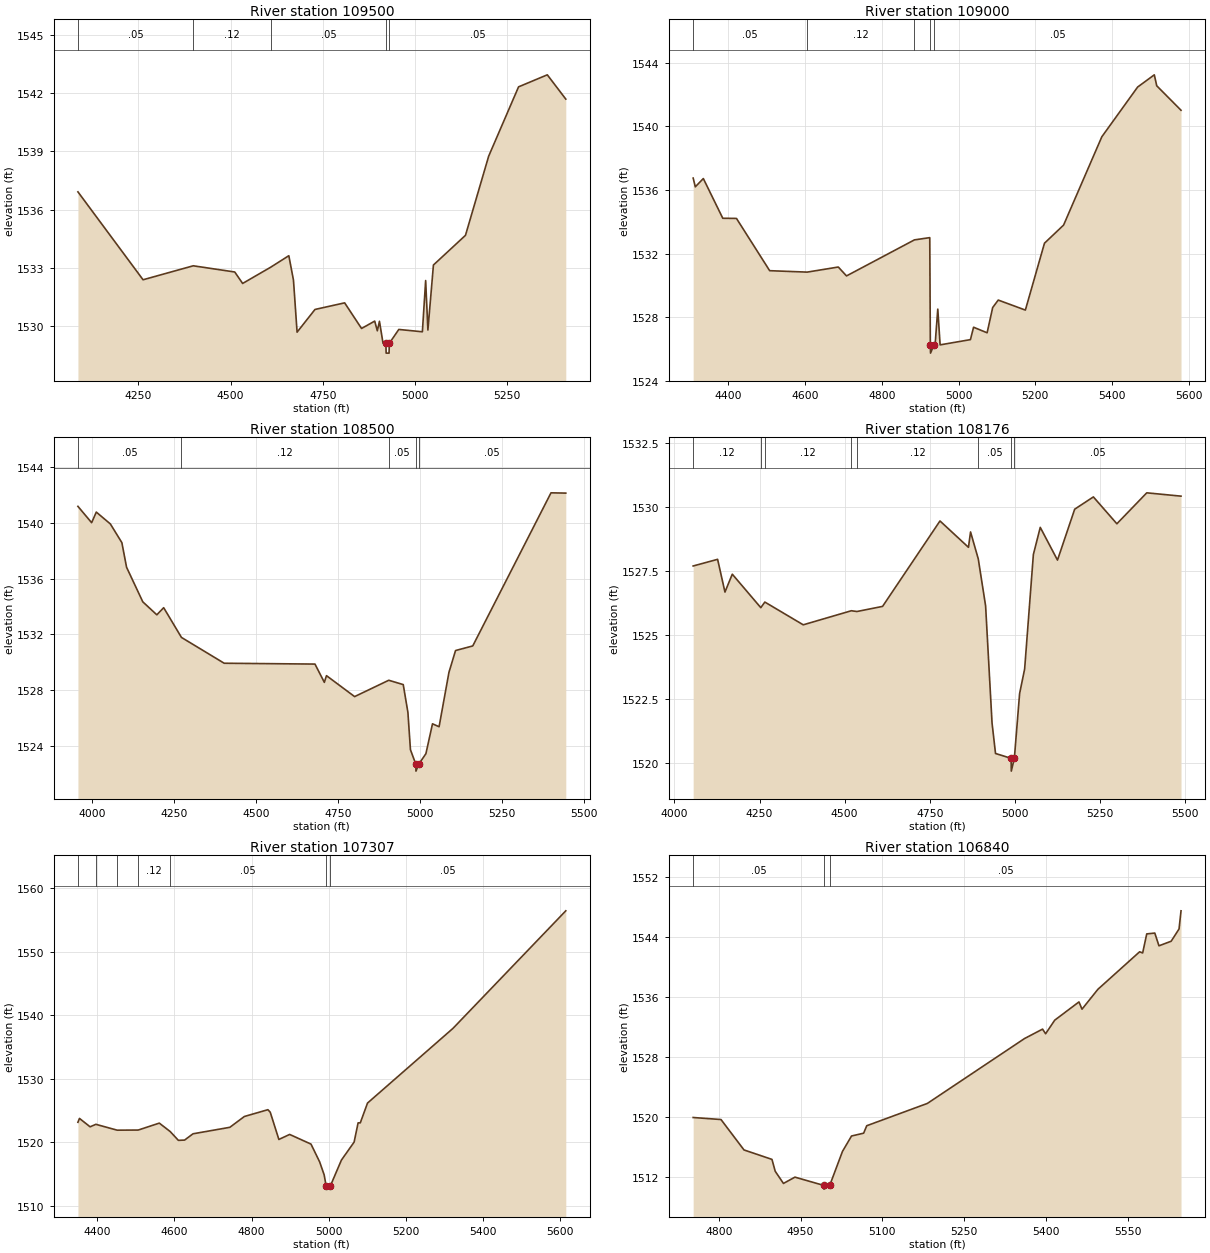
Type RM Length L Ch R = 1 ,109500  ,500,500,500
BEGIN DESCRIPTION:
HICKORY CREEK 219.0
END DESCRIPTION:
XS GIS Cut Line= 3
      2745622.58     10153831.94       2746092.3     10154616.47
      2746320.52     10154956.96
#Sta/Elev= 30
  4085.6 1536.91  4262.4 1532.38  4398.7  1533.1  4511.3 1532.78  4532.7 1532.19
  4609.1 1533.03  4658.1 1533.62  4670.7 1532.36  4680.5 1529.68  4729.1 1530.85
  4809.6 1531.19  4855.5 1529.87  4891.2 1530.25  4898.3 1529.75  4904.1 1530.24
  4913.8 1529.11  4921.7  1529.1  4922.2  1528.6  4930.2  1528.6  4930.7  1529.1
  4956.6 1529.82  5020.6  1529.7  5029.5 1532.34  5035.6 1529.79  5050.6 1533.14
  5137.6 1534.67  5200.6 1538.75  5281.7 1542.32  5359.7 1542.94  5409.9 1541.69
#Mann= 5 ,-1 , 0
  4085.6     .05       0  4398.7     .12       0  4609.1     .05       0
  4921.7     .05       0  4930.7     .05       0
Bank Sta=4921.7,4930.7
XS Rating Curve= 0 ,0
Exp/Cntr=0.3,0.1

Type RM Length L Ch R = 1 ,109000  ,500,500,500
BEGIN DESCRIPTION:
HICKORY CREEK 218.0
END DESCRIPTION:
XS GIS Cut Line= 3
      2745346.56     10154154.89      2745741.34     10154722.87
      2746200.73     10155076.77
#Sta/Elev= 30
  4308.3 1536.75  4313.9  1536.2  4334.8 1536.72  4385.5 1534.22  4421.2 1534.21
  4507.7 1530.92  4605.4 1530.83  4686.6 1531.15    4708 1530.59  4885.1 1532.86
    4925    1533  4926.5 1526.23    4927 1525.73  4935.6 1526.23  4939.4 1526.42
  4945.9  1528.5    4952 1526.25    5031 1526.58  5039.2 1527.36  5074.5 1527.01
    5089  1528.6  5103.5 1529.07  5174.2 1528.44    5224 1532.65  5273.8 1533.79
  5373.5 1539.35  5466.8 1542.48  5510.3 1543.25  5516.6 1542.56  5579.9 1541.02
#Mann= 5 ,-1 , 0
  4308.3     .05       0  4605.4     .12       0  4885.1     .05       0
  4926.5     .03       0  4935.6     .05       0
Bank Sta=4926.5,4935.6
XS Rating Curve= 0 ,0
Exp/Cntr=0.3,0.1

Type RM Length L Ch R = 1 ,108500  ,324,324,324
BEGIN DESCRIPTION:
HICKORY CREEK 217.0
END DESCRIPTION:
XS GIS Cut Line= 3
      2744993.72     10154366.23      2745667.36     10155162.25
      2746110.59     10155122.58
#Sta/Elev= 30
  3957.2 1541.17    3999    1540  4013.2 1540.76  4056.1 1539.91  4091.2 1538.57
  4105.5 1536.81    4155 1534.33  4197.8  1533.4  4218.7 1533.91  4272.9 1531.78
  4403.2 1529.93  4680.1 1529.87  4708.7 1528.56  4715.2 1529.04    4801 1527.54
  4905.1 1528.71  4949.3  1528.4  4963.5 1526.41  4971.3 1523.73  4987.6  1522.7
  4988.1  1522.2  4996.7  1522.7  5018.4 1523.45  5038.5 1525.59  5058.6 1525.38
  5088.7 1529.28  5108.8 1530.84  5161.3 1531.17  5399.9 1542.14    5445 1542.12
#Mann= 5 ,-1 , 0
  3957.2     .05       0  4272.9     .12       0  4905.1     .05       0
  4987.6     .05       0  4996.7     .05       0
Bank Sta=4987.6,4996.7
XS Rating Curve= 0 ,0
Exp/Cntr=0.3,0.1

Type RM Length L Ch R = 1 ,108176  ,869,869,869
BEGIN DESCRIPTION:
Mapping XS a47c8ca9
END DESCRIPTION:
XS GIS Cut Line= 4
      2744678.96     10155148.86      2745473.19     10155465.69
      2745876.84     10155404.92      2746046.13     10155396.24
#Sta/Elev= 30
  4055.1  1527.7  4126.9 1527.96  4148.5 1526.68    4170 1527.38  4253.8 1526.07
  4265.6 1526.29  4378.4  1525.4  4519.7 1525.95  4536.1 1525.92  4611.4 1526.12
    4780 1529.46  4863.6 1528.43  4869.8 1529.03  4892.4 1527.98    4914 1526.14
  4932.9 1521.56  4943.1 1520.37  4988.9 1520.18  4989.4 1519.68  4998.4 1520.18
  5013.8 1522.71  5028.6 1523.67  5054.3 1528.15  5074.5 1529.21  5125.1 1527.93
  5175.6 1529.92  5230.5  1530.4  5299.5 1529.35  5387.3 1530.56  5487.9 1530.43
#Mann= 8 ,-1 , 0
  4055.1     .12       0  4253.8     .05       0  4265.6     .12       0
  4519.7     .05       0  4536.1     .12       0  4892.4     .05       0
  4988.9     .05       0  4998.4     .05       0
Bank Sta=4988.9,4998.4
XS Rating Curve= 0 ,0
Exp/Cntr=0.3,0.1

Type RM Length L Ch R = 1 ,107307  ,467,467,467
BEGIN DESCRIPTION:
Mapping XS 95c73bb7
END DESCRIPTION:
XS GIS Cut Line= 4
      2744809.14     10155765.17      2745152.01      10155951.8
      2745303.92     10156255.62      2745724.93     10156585.48
#Sta/Elev= 30
  4349.7 1523.16  4353.7 1523.77  4381.2 1522.45  4396.3 1522.84  4451.4 1521.92
  4506.1 1521.94  4560.7 1523.03  4589.2 1521.69  4610.1 1520.32  4626.2 1520.36
  4648.1 1521.35  4743.6 1522.37  4781.2 1524.07  4842.2 1525.14  4848.3 1524.75
  4870.7 1520.46  4898.6 1521.25    4954 1519.73  4976.3 1516.95  4988.1  1514.9
  4993.2 1513.15  4993.7 1512.65  5004.2 1513.15  5032.8 1517.21  5065.8 1520.05
  5076.1 1523.07  5081.8 1523.07  5100.5 1526.18    5322 1537.92  5614.6 1556.41
#Mann= 7 ,-1 , 0
  4349.7     .05       0  4396.3     .12       0  4451.4     .05       0
  4506.1     .12       0  4589.2     .05       0  4993.2     .05       0
  5004.2     .05       0
Bank Sta=4993.2,5004.2
XS Rating Curve= 0 ,0
Exp/Cntr=0.3,0.1

Type RM Length L Ch R = 1 ,106840  ,192,192,192
BEGIN DESCRIPTION:
Mapping XS 91b1895d
END DESCRIPTION:
XS GIS Cut Line= 3
      2744731.03     10156207.91      2744869.89     10156420.55
      2745441.78     10156710.82
#Sta/Elev= 30
  4752.9 1519.96    4804 1519.69  4846.2 1515.63  4897.5 1514.37  4903.5 1512.78
  4918.6 1511.16  4939.7    1512  4992.4  1510.9  4992.9  1510.4  5003.5  1510.9
  5026.9 1515.43  5043.5 1517.49  5065.8 1517.87  5071.4 1518.86  5182.7 1521.84
    5361  1530.5  5394.1 1531.76  5399.7 1531.14  5416.4 1532.95  5460.9 1535.39
  5466.5 1534.42  5495.6 1537.07  5572.2 1542.08  5577.8 1541.93  5585.3 1544.47
  5600.1 1544.58  5607.7 1542.88  5630.1 1543.49  5644.6 1545.13  5648.2 1547.55
#Mann= 3 ,-1 , 0
  4752.9     .05       0  4992.4     .03       0  5003.5     .05       0
Bank Sta=4992.4,5003.5
XS Rating Curve= 0 ,0
Exp/Cntr=0.3,0.1

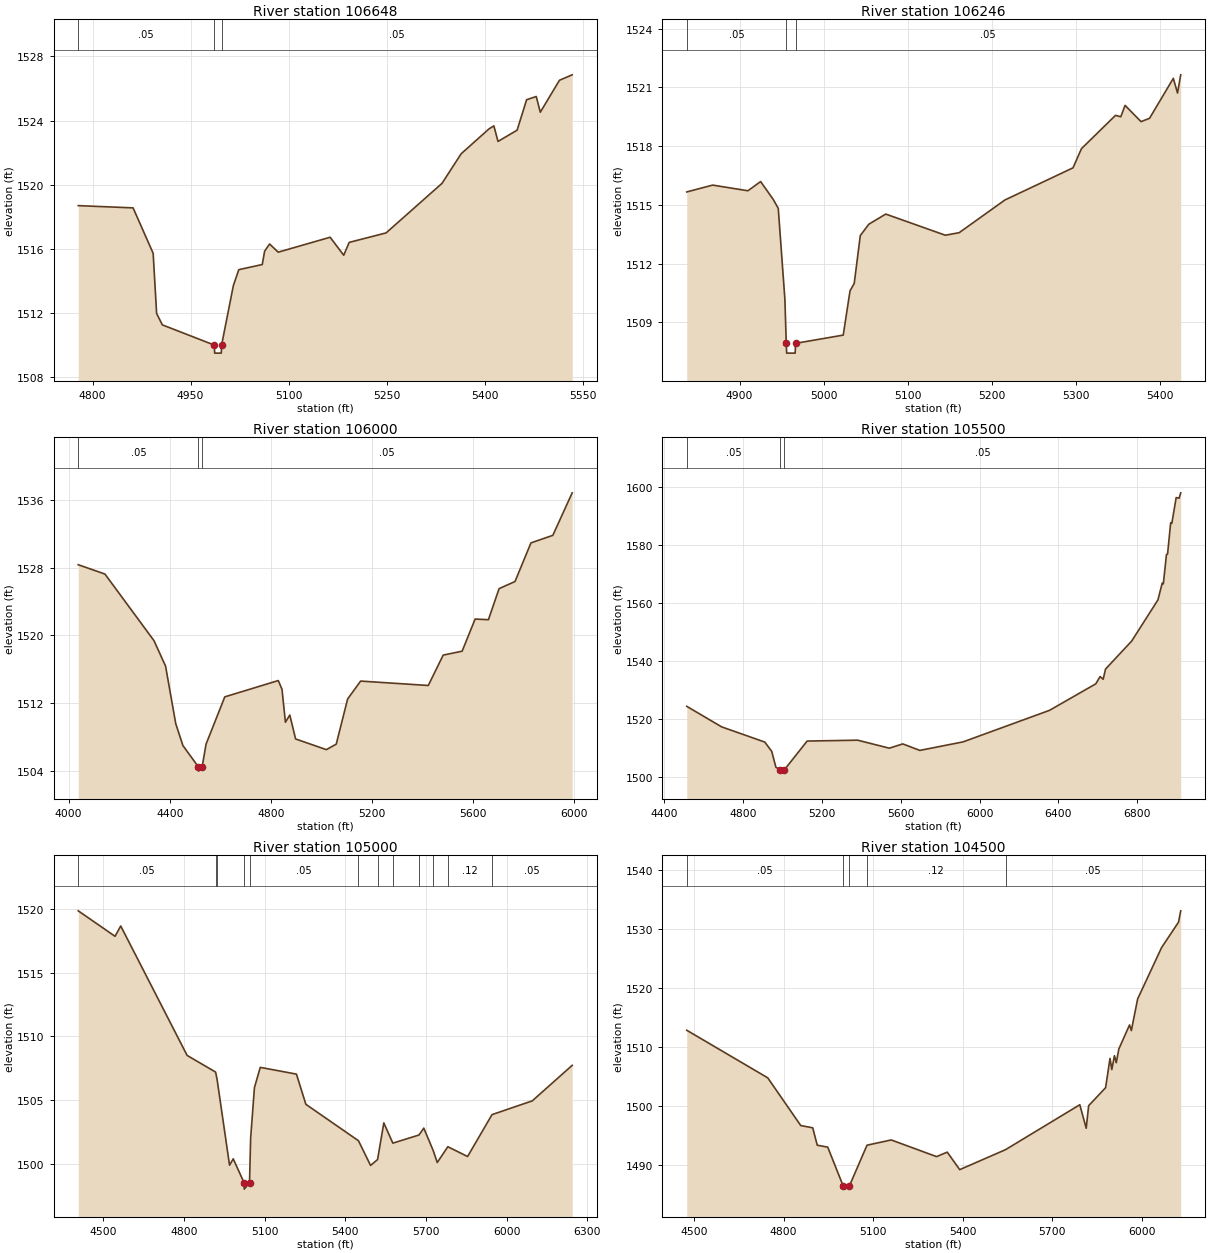
Type RM Length L Ch R = 1 ,106648  ,402,402,402
BEGIN DESCRIPTION:
Mapping XS 483a32d5
END DESCRIPTION:
XS GIS Cut Line= 3
      2744631.18     10156312.04      2744726.66      10156576.8
      2745108.05      10156858.5
#Sta/Elev= 30
  4778.1  1518.7    4862 1518.56  4892.7 1515.73    4898 1511.98  4906.8 1511.27
  4986.3 1510.01  4986.8 1509.51  4996.9 1509.51  4997.4 1510.01  5015.4 1513.72
  5023.7 1514.71  5059.6 1515.03  5063.2 1515.86  5070.8 1516.31    5084  1515.8
  5163.4 1516.73  5184.2 1515.61  5192.6 1516.41    5249    1517  5334.6 1520.09
  5363.8 1521.93  5406.4 1523.48  5413.9 1523.67  5420.2  1522.7  5449.4  1523.4
    5464  1525.3  5478.7  1525.5  5484.9 1524.52  5514.2 1526.51  5533.7 1526.85
#Mann= 3 ,-1 , 0
  4778.1     .05       0  4986.3     .03       0  4997.4     .05       0
Bank Sta=4986.3,4997.4
XS Rating Curve= 0 ,0
Exp/Cntr=0.3,0.1

Type RM Length L Ch R = 1 ,106246  ,246,246,246
BEGIN DESCRIPTION:
Mapping XS 1c0c6f32
END DESCRIPTION:
XS GIS Cut Line= 3
      2744418.54     10156728.73      2744561.73     10156824.19
      2744972.35     10156889.03
#Sta/Elev= 30
  4837.2 1515.66    4868 1516.01    4910 1515.72  4925.1 1516.19  4940.1 1515.28
  4946.1 1514.82    4954 1510.17  4955.6 1507.93  4956.1 1507.43  4966.2 1507.43
  4966.7 1507.93  5023.4 1508.35  5031.5 1510.61  5036.5 1510.99  5043.7 1513.43
  5053.8 1514.01    5074 1514.53  5144.9 1513.45  5161.4 1513.58  5215.8 1515.25
  5296.8 1516.89  5306.9 1517.87  5347.4 1519.57  5353.7  1519.5  5358.8 1520.08
  5377.8 1519.25  5387.9 1519.42  5416.2 1521.46  5421.2 1520.71    5425 1521.64
#Mann= 3 ,-1 , 0
  4837.2     .05       0  4955.6     .03       0  4966.7     .05       0
Bank Sta=4955.6,4966.7
XS Rating Curve= 0 ,0
Exp/Cntr=0.3,0.1

Type RM Length L Ch R = 1 ,106000  ,500,500,500
BEGIN DESCRIPTION:
HICKORY CREEK 212.0
END DESCRIPTION:
XS GIS Cut Line= 3
      2743655.71     10156653.12      2744527.18     10157059.59
      2745471.01     10157362.35
#Sta/Elev= 30
  4038.4 1528.33    4144 1527.23  4337.9 1519.38  4383.7 1516.38  4423.9  1509.6
  4452.3 1507.02  4513.5 1504.51    4514 1504.01  4528.2 1504.51  4543.7 1507.19
  4617.8 1512.76  4829.1 1514.68  4843.9 1513.66  4857.5 1509.77  4874.8 1510.62
  4897.7  1507.8  5019.4 1506.54  5058.4 1507.19  5103.4 1512.51  5154.8 1514.62
  5422.3  1514.1  5481.2 1517.68    5556 1518.14  5607.5 1521.93    5660 1521.85
  5702.1 1525.51  5765.1 1526.35  5828.1  1530.9  5914.6 1531.79  5991.2  1536.8
#Mann= 3 ,-1 , 0
  4038.4     .05       0  4513.5     .03       0  4528.2     .05       0
Bank Sta=4513.5,4528.2
XS Rating Curve= 0 ,0
Exp/Cntr=0.3,0.1

Type RM Length L Ch R = 1 ,105500  ,500,500,500
BEGIN DESCRIPTION:
HICKORY CREEK 211.0
END DESCRIPTION:
XS GIS Cut Line= 3
      2743755.71     10156853.14      2744107.74     10157188.65
      2745855.68     10158203.11
#Sta/Elev= 30
  4513.7 1524.34  4690.6 1517.27  4909.8 1512.03    4945 1508.83  4966.4 1503.33
  4989.5 1502.53    4990 1502.03  5009.7 1502.53  5124.8 1512.38  5381.2 1512.68
  5541.8 1509.93  5610.4  1511.4  5696.7 1509.16  5916.1 1512.09  6354.9 1522.95
  6590.1 1532.08  6611.6 1534.59  6627.3 1533.66  6639.5 1537.17  6772.2 1546.81
  6905.4 1560.97    6927 1566.73  6932.8 1566.48  6948.6 1576.58  6954.3  1576.8
  6970.1 1587.56  6975.9 1587.32  6997.9 1596.18  7013.1    1596    7021 1597.83
#Mann= 3 ,-1 , 0
  4513.7     .05       0  4989.5     .05       0  5009.7     .05       0
Bank Sta=4989.5,5009.7
XS Rating Curve= 0 ,0
Exp/Cntr=0.3,0.1

Type RM Length L Ch R = 1 ,105000  ,500,500,500
BEGIN DESCRIPTION:
HICKORY CREEK 210.0
END DESCRIPTION:
XS GIS Cut Line= 3
      2743505.69     10157103.12      2743832.33     10157598.65
      2744756.14     10158431.93
#Sta/Elev= 30
  4406.5 1519.85  4543.5 1517.85  4564.6 1518.66  4811.5  1508.5  4917.5 1507.19
  4922.8 1506.65  4969.4 1499.88  4983.1 1500.38  5023.5  1498.5    5024    1498
  5043.7  1498.5  5047.8 1501.99    5062 1505.97  5083.7 1507.56  5218.2 1507.03
  5253.3 1504.66    5449  1501.8    5494 1499.86    5520 1500.32  5543.3  1503.2
  5576.9 1501.61  5674.2 1502.25    5692 1502.79    5727 1501.03  5742.1 1500.09
  5781.5 1501.33  5854.9 1500.56  5945.9 1503.85  6095.6 1504.93  6244.1 1507.72
#Mann= 12 ,-1 , 0
  4406.5     .05       0  4917.5     .12       0  4922.8     .05       0
  5023.5     .05       0  5043.7     .05       0    5449      .1       0
    5520     .12       0  5576.9      .1       0  5674.2     .12       0
    5727     .05       0  5781.5     .12       0  5945.9     .05       0
Bank Sta=5023.5,5043.7
XS Rating Curve= 0 ,0
Exp/Cntr=0.3,0.1

Type RM Length L Ch R = 1 ,104500  ,500,500,500
BEGIN DESCRIPTION:
HICKORY CREEK 209.0
END DESCRIPTION:
XS GIS Cut Line= 3
      2743455.69     10157453.15      2743509.62     10157974.66
      2744155.68      10158903.1
#Sta/Elev= 30
  4475.7 1512.85  4747.1 1504.77  4857.7 1496.67  4897.9 1496.28    4913 1493.33
  4948.2    1493  5000.2 1486.37  5000.7 1485.87  5020.4 1486.37  5079.8 1493.33
    5161 1494.22  5312.9 1491.39  5348.7 1492.15  5390.5 1489.18    5544 1492.57
  5792.9  1500.2  5814.4 1496.21  5822.6 1500.04  5879.3 1503.09  5894.2 1508.07
  5900.2 1506.18    5909 1508.53  5915.1 1507.34  5923.8 1509.68  5959.6 1513.75
  5965.7  1512.8  5986.7 1518.16    6067 1526.89  6123.7  1531.2  6131.1 1533.13
#Mann= 5 ,-1 , 0
  4475.7     .05       0  5000.2     .05       0  5020.4     .05       0
  5079.8     .12       0    5544     .05       0
Bank Sta=5000.2,5020.4
XS Rating Curve= 0 ,0
Exp/Cntr=0.3,0.1