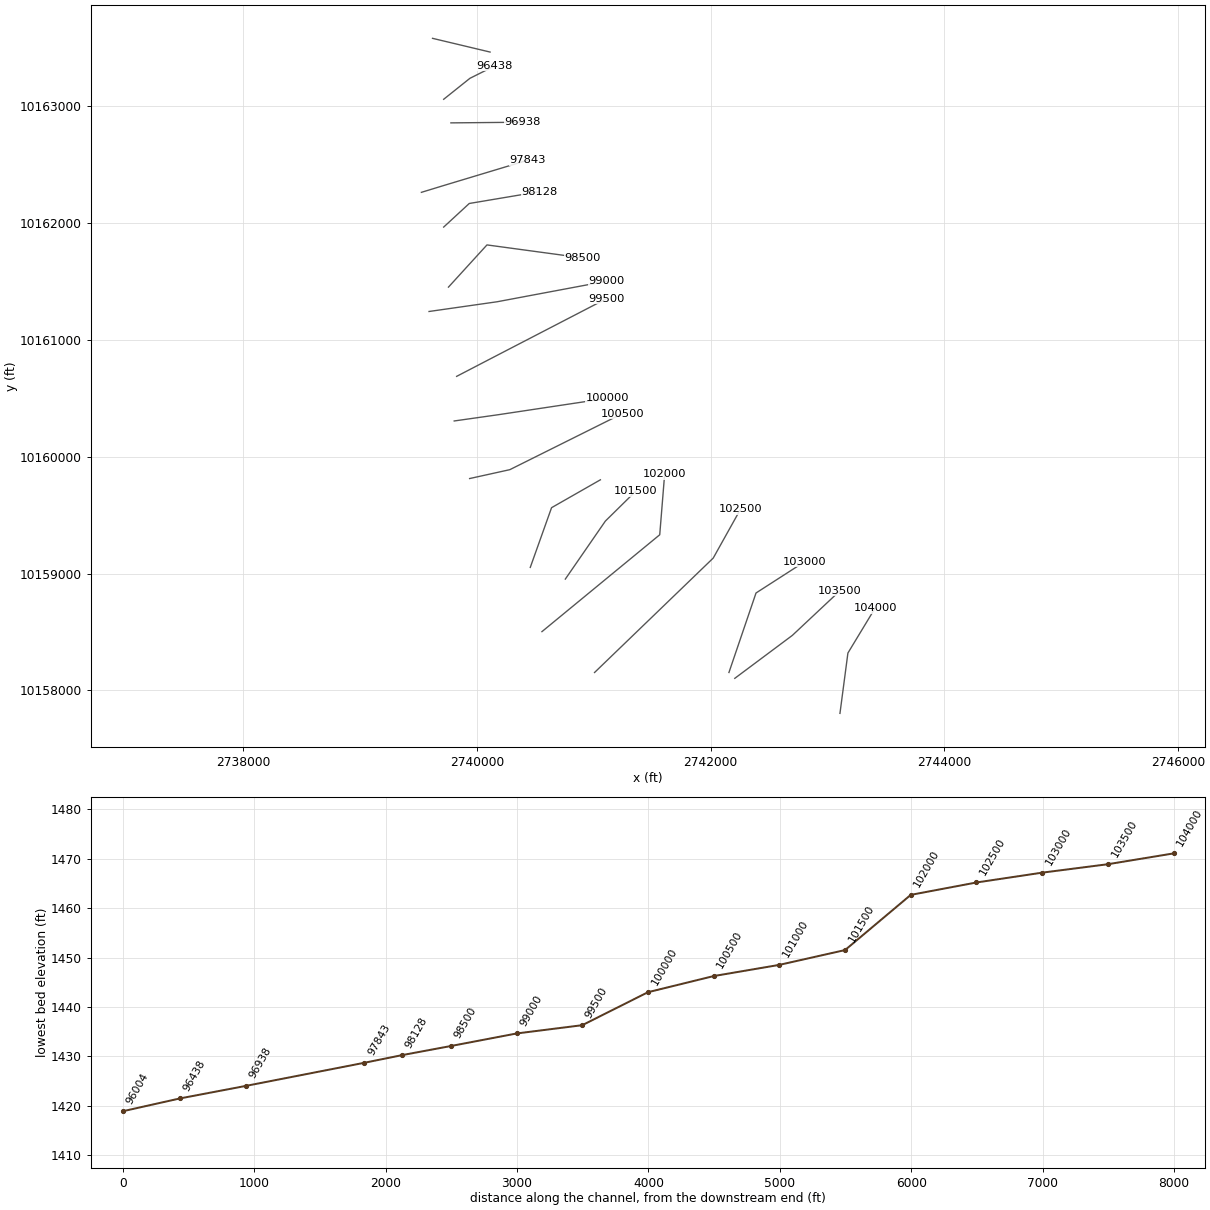
HEC-RAS study HICKORY CREEK.prj: HICKORY CREEK Base Level Engineering

--- HICKORY CREEK.g01 (geometry) --- (continued)

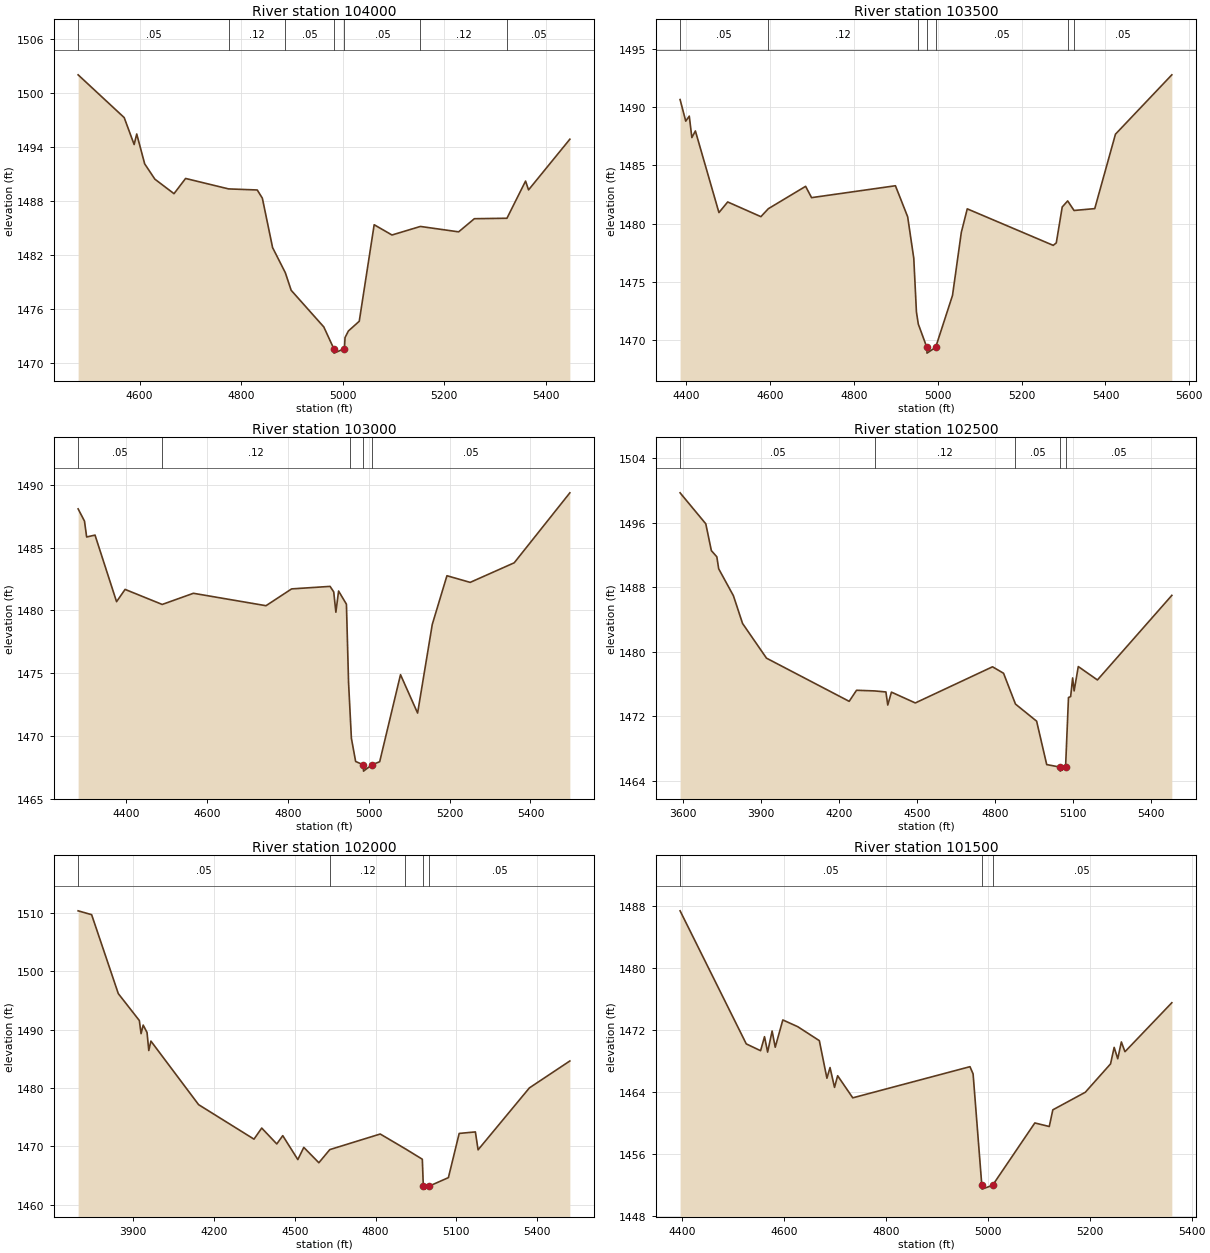
Type RM Length L Ch R = 1 ,104000  ,500,500,500
BEGIN DESCRIPTION:
HICKORY CREEK 208.0
END DESCRIPTION:
XS GIS Cut Line= 3
      2743105.68     10157803.08      2743173.75     10158319.81
      2743405.68     10158703.11
#Sta/Elev= 30
  4478.8    1502  4569.6 1497.25  4589.2 1494.26  4594.3 1495.43    4610 1492.11
  4630.1 1490.41  4667.8  1488.8  4690.6 1490.49  4775.3 1489.33  4831.9 1489.21
  4841.9  1488.3  4862.1 1482.81  4887.2 1480.02  4898.7 1478.07    4963    1474
  4982.7 1471.59  4983.2 1471.09  5003.7 1471.59  5004.9 1472.82  5011.5 1473.55
  5032.9 1474.63  5062.3 1485.35  5097.4 1484.21  5153.4 1485.16  5228.8 1484.56
  5259.8 1486.02    5324 1486.07  5360.7  1490.2  5366.6 1489.22    5448 1494.85
#Mann= 7 ,-1 , 0
  4478.8     .05       0  4775.3     .12       0  4887.2     .05       0
  4982.7     .05       0  5003.7     .05       0  5153.4     .12       0
    5324     .05       0
Bank Sta=4982.7,5003.7
XS Rating Curve= 0 ,0
Exp/Cntr=0.3,0.1

Type RM Length L Ch R = 1 ,103500  ,500,500,500
BEGIN DESCRIPTION:
HICKORY CREEK 207.0
END DESCRIPTION:
XS GIS Cut Line= 3
      2742205.71     10158103.13      2742698.42     10158471.01
      2743105.65     10158853.08
#Sta/Elev= 30
  4385.1 1490.64  4398.6 1488.79    4407 1489.22  4413.2 1487.38  4421.6 1487.95
  4477.8 1480.95  4498.7 1481.86  4577.9  1480.6  4595.6 1481.28  4684.6  1483.2
  4698.8 1482.23  4898.9 1483.25  4928.1 1480.59  4942.7 1477.03    4949 1472.43
  4953.5 1471.39  4973.8  1469.4  4974.3  1468.9  4994.9  1469.4  5035.1 1473.85
  5056.1 1479.25  5070.3 1481.27  5275.4 1478.14  5282.7 1478.35  5296.9 1481.43
  5309.9 1481.95  5325.1 1481.13  5374.5 1481.29  5423.9 1487.67  5558.4 1492.76
#Mann= 7 ,-1 , 0
  4385.1     .05       0  4595.6     .12       0  4953.5     .05       0
  4973.8     .05       0  4994.9     .05       0  5309.9     .12       0
  5325.1     .05       0
Bank Sta=4973.8,4994.9
XS Rating Curve= 0 ,0
Exp/Cntr=0.3,0.1

Type RM Length L Ch R = 1 ,103000  ,500,500,500
BEGIN DESCRIPTION:
HICKORY CREEK 206.0
END DESCRIPTION:
XS GIS Cut Line= 3
      2742155.68     10158153.09      2742387.39     10158833.94
      2742805.67      10159103.1
#Sta/Elev= 30
  4280.8  1488.1  4296.5 1487.13  4301.9 1485.86  4322.6 1486.01  4375.9  1480.7
    4397 1481.68  4488.8 1480.48    4566 1481.37  4745.6 1480.38    4809 1481.72
  4904.1 1481.92  4913.2 1481.48  4918.5 1479.86  4925.2 1481.55  4944.6  1480.5
  4949.9 1474.24  4952.6 1472.53  4956.9 1469.81  4967.4 1467.96  4986.4 1467.69
  4986.9 1467.19  5007.5 1467.69  5026.9 1467.94  5078.4 1474.88  5120.7 1471.82
    5157 1478.89  5193.3 1482.77  5250.8 1482.24  5359.7  1483.8  5497.4 1489.38
#Mann= 5 ,-1 , 0
  4280.8     .05       0  4488.8     .12       0  4952.6     .05       0
  4986.4     .05       0  5007.5     .05       0
Bank Sta=4986.4,5007.5
XS Rating Curve= 0 ,0
Exp/Cntr=0.3,0.1

Type RM Length L Ch R = 1 ,102500  ,500,500,500
BEGIN DESCRIPTION:
HICKORY CREEK 205.0
END DESCRIPTION:
XS GIS Cut Line= 3
      2741005.67     10158153.09      2742021.36      10159133.1
      2742255.71     10159553.15
#Sta/Elev= 30
  3588.6 1499.69  3687.5 1495.85  3708.9 1492.53    3730 1491.76  3737.2 1490.27
  3793.8 1486.94    3829  1483.5  3921.1  1479.2  4239.3 1473.85  4267.6 1475.22
  4337.3 1475.14  4380.7 1475.01  4387.8 1473.39  4401.9 1474.99  4493.8 1473.65
  4790.9 1478.13  4833.4 1477.33  4879.3 1473.51  4960.7 1471.39  4999.5 1466.01
    5051  1465.7  5051.5  1465.2  5072.1  1465.7  5083.3 1474.32  5091.6 1474.44
  5099.3 1476.75    5105 1475.14    5121 1478.16  5194.7  1476.5    5481 1486.98
#Mann= 5 ,-1 , 0
  3588.6     .05       0  4337.3     .12       0  4879.3     .05       0
    5051     .05       0  5072.1     .05       0
Bank Sta=5051,5072.1
XS Rating Curve= 0 ,0
Exp/Cntr=0.3,0.1

Type RM Length L Ch R = 1 ,102000  ,500,500,500
BEGIN DESCRIPTION:
HICKORY CREEK 204.0
END DESCRIPTION:
XS GIS Cut Line= 3
      2740555.65     10158503.09      2741563.45     10159332.48
      2741605.68     10159853.07
#Sta/Elev= 30
  3694.8 1510.36    3745  1509.7  3844.1 1496.18  3922.3 1491.57  3928.7 1489.32
  3936.6 1490.79  3950.9 1489.52  3957.4 1486.43  3965.3 1488.05  4142.5 1477.16
  4348.4 1471.25  4377.1 1473.15  4433.1 1470.43  4455.3 1471.85  4511.3 1467.75
  4533.5 1469.84  4589.5 1467.21  4630.1 1469.46  4817.6 1472.13  4911.4 1469.58
    4974 1467.81  4977.7 1463.19  4978.2 1462.69  4998.8 1463.19  5070.9 1464.66
    5111 1472.23  5171.2 1472.49  5181.2 1469.42  5371.9 1480.03  5522.3 1484.64
#Mann= 5 ,-1 , 0
  3694.8     .05       0  4630.1     .12       0  4911.4     .05       0
  4977.7     .03       0  4998.8     .05       0
Bank Sta=4977.7,4998.8
XS Rating Curve= 0 ,0
Exp/Cntr=0.3,0.1

Type RM Length L Ch R = 1 ,101500  ,500,500,500
BEGIN DESCRIPTION:
HICKORY CREEK 203.0
END DESCRIPTION:
XS GIS Cut Line= 3
      2740755.69     10158953.13      2741098.35     10159449.79
      2741355.69     10159703.11
#Sta/Elev= 30
  4396.6 1487.42  4526.4 1470.25  4554.5 1469.37  4562.2 1471.18  4568.3 1469.19
  4577.1 1471.91  4583.2 1469.82  4598.1 1473.34  4627.4 1472.47  4669.7 1470.67
  4684.6 1465.82  4690.7  1467.2  4699.5 1464.64  4705.6 1466.14  4735.3 1463.29
  4965.2 1467.31  4971.3 1466.38  4988.4 1452.01  4988.9 1451.51  5009.6 1452.01
  5092.4 1460.05  5120.7 1459.59  5127.7 1461.74  5191.4 1464.01  5240.9 1467.67
    5248  1469.8    5255 1468.33  5262.1  1470.5  5269.2 1469.24  5361.1 1475.56
#Mann= 3 ,-1 , 0
  4396.6     .05       0  4988.4     .05       0  5009.6     .05       0
Bank Sta=4988.4,5009.6
XS Rating Curve= 0 ,0
Exp/Cntr=0.3,0.1

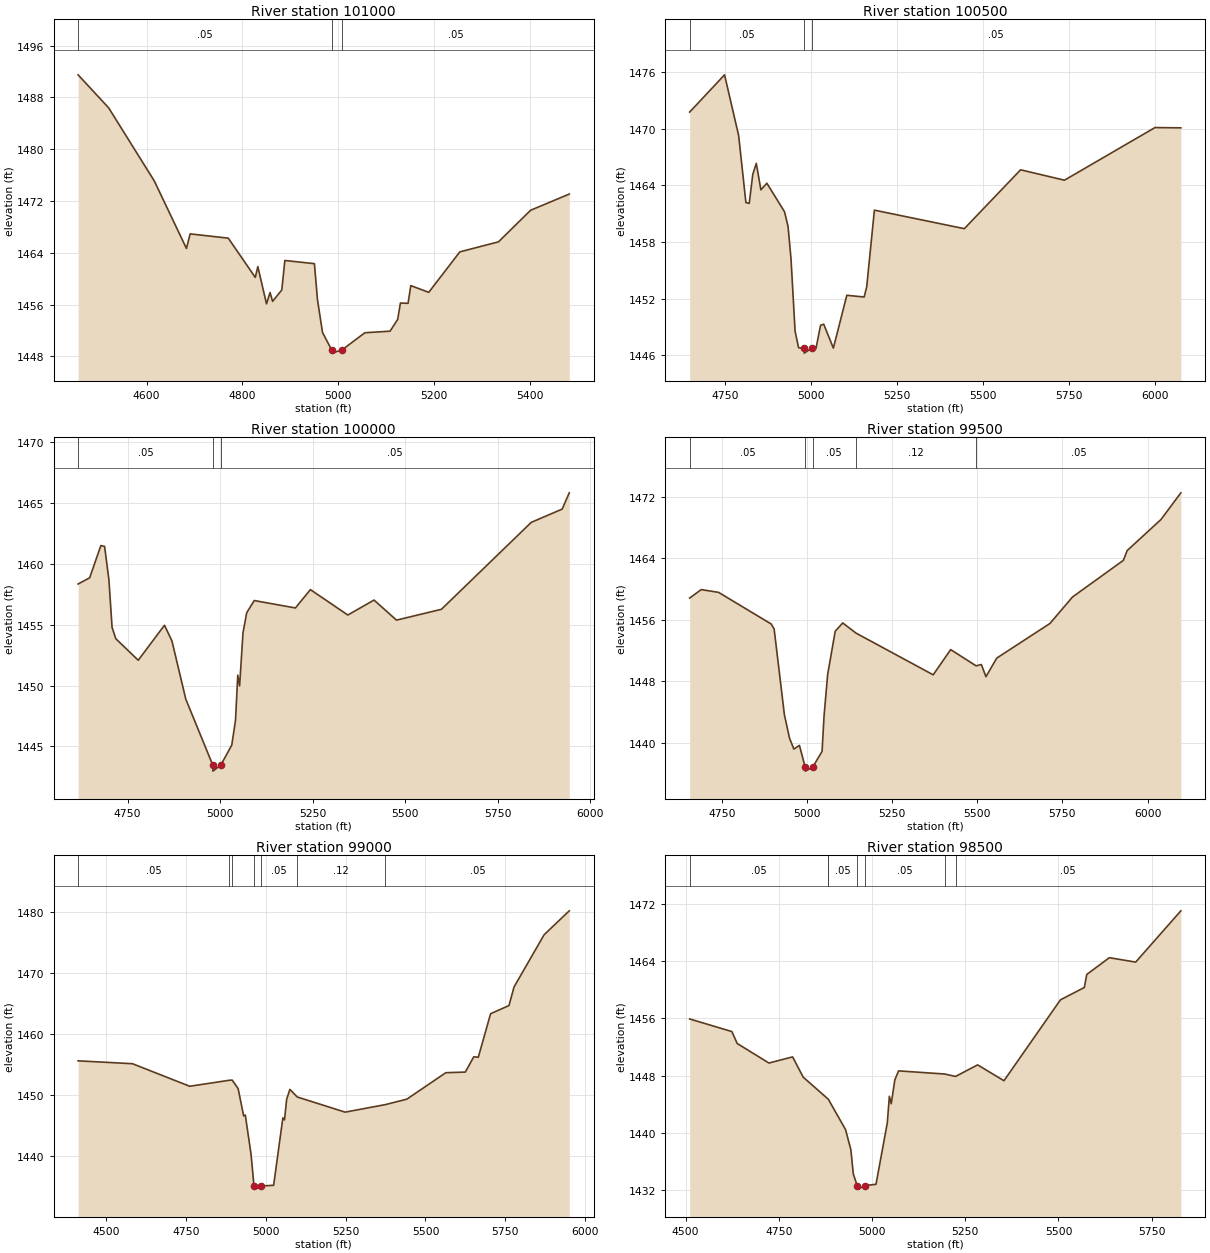
Type RM Length L Ch R = 1 ,101000  ,500,500,500
BEGIN DESCRIPTION:
HICKORY CREEK 202.0
END DESCRIPTION:
XS GIS Cut Line= 3
      2740455.67     10159053.07      2740637.79      10159564.3
      2741055.67      10159803.1
#Sta/Elev= 30
  4457.3  1491.5    4521  1486.4  4616.3 1475.09  4683.2 1464.68  4690.9 1466.93
  4770.4 1466.27  4826.7 1460.21    4832 1461.88  4850.1 1456.12  4857.5 1457.87
  4862.8  1456.5    4882 1458.28  4888.3 1462.82    4950 1462.33  4956.3 1456.79
  4966.9 1451.69  4985.9 1449.01  4986.4 1448.51  5007.6 1449.01  5055.2 1451.66
  5107.7  1451.9  5123.6 1453.73  5129.3 1456.25  5145.2  1456.2  5150.9 1458.94
  5188.3  1457.9  5253.1 1464.15  5333.7  1465.7  5400.7 1470.58  5481.3 1473.08
#Mann= 3 ,-1 , 0
  4457.3     .05       0  4985.9     .03       0  5007.6     .05       0
Bank Sta=4985.9,5007.6
XS Rating Curve= 0 ,0
Exp/Cntr=0.3,0.1

Type RM Length L Ch R = 1 ,100500  ,500,500,500
BEGIN DESCRIPTION:
HICKORY CREEK 201.0
END DESCRIPTION:
XS GIS Cut Line= 3
      2739936.73     10159813.88      2740280.53     10159889.85
      2741242.28     10160369.44
#Sta/Elev= 30
  4647.9 1471.75  4749.2 1475.69  4790.2 1469.26  4811.2 1462.17  4820.9 1462.09
  4831.2 1465.15  4841.4 1466.32  4854.8 1463.52  4872.1 1464.22  4923.3 1461.21
  4933.6 1459.66  4942.2 1456.26  4954.1 1448.56  4964.3 1446.82  4980.1 1446.74
  4980.6 1446.24  5001.8 1446.74  5014.9 1446.75  5028.1 1449.19  5037.3  1449.3
  5065.3 1446.77  5104.4 1452.36  5154.8 1452.18  5162.2 1453.27  5184.5 1461.37
  5445.7 1459.41  5609.2 1465.64  5736.6 1464.54  5999.6 1470.11  6074.7 1470.08
#Mann= 3 ,-1 , 0
  4647.9     .05       0  4980.1     .03       0  5001.8     .05       0
Bank Sta=4980.1,5001.8
XS Rating Curve= 0 ,0
Exp/Cntr=0.3,0.1

Type RM Length L Ch R = 1 ,100000  ,500,500,500
BEGIN DESCRIPTION:
HICKORY CREEK 200.0
END DESCRIPTION:
XS GIS Cut Line= 3
      2739804.75     10160306.93      2740184.54     10160360.86
      2741117.21     10160501.37
#Sta/Elev= 30
  4616.4 1458.36  4647.6 1458.87  4677.9 1461.52    4688 1461.45  4699.6 1458.72
  4708.2 1454.79  4718.3 1453.86  4778.9 1452.09  4849.7 1454.97  4869.9 1453.68
  4907.3 1448.89  4980.2 1443.47  4980.7 1442.97  5001.9 1443.47  5031.5 1445.11
  5041.6 1447.15  5047.7 1450.86  5052.7 1449.98  5061.8 1454.34  5071.9    1456
  5092.2    1457  5203.4 1456.39  5243.9  1457.9    5345 1455.81  5415.8 1457.04
  5476.5 1455.39  5597.8 1456.28  5840.5 1463.43  5923.9 1464.52  5943.2 1465.86
#Mann= 3 ,-1 , 0
  4616.4     .05       0  4980.2     .03       0  5001.9     .05       0
Bank Sta=4980.2,5001.9
XS Rating Curve= 0 ,0
Exp/Cntr=0.3,0.1

Type RM Length L Ch R = 1 ,99500   ,500,500,500
BEGIN DESCRIPTION:
HICKORY CREEK 199.0
END DESCRIPTION:
XS GIS Cut Line= 3
      2739825.63     10160688.89      2740130.99     10160847.73
      2741105.66      10161353.1
#Sta/Elev= 30
  4655.8 1458.81  4689.7 1459.91  4740.6 1459.55  4895.3 1455.43  4903.8 1454.78
  4933.9 1443.63  4948.9 1440.59  4961.7 1439.16  4978.1 1439.64    4995 1436.79
  4995.5 1436.29  5016.7 1436.79  5044.5 1438.86  5050.3 1443.46    5061 1448.89
  5083.1 1454.49  5105.2 1455.57  5144.1 1454.25  5370.8 1448.82  5422.1  1452.1
  5496.7 1449.99  5512.2 1450.16  5525.7 1448.57  5557.2 1450.99  5713.5  1455.5
  5779.9 1458.95    5929 1463.71  5940.4 1464.99  6039.8 1469.04  6097.9  1472.5
#Mann= 5 ,-1 , 0
  4655.8     .05       0    4995     .05       0  5016.7     .05       0
  5144.1     .12       0  5496.7     .05       0
Bank Sta=4995,5016.7
XS Rating Curve= 0 ,0
Exp/Cntr=0.3,0.1

Type RM Length L Ch R = 1 ,99000   ,500,500,500
BEGIN DESCRIPTION:
HICKORY CREEK 198.0
END DESCRIPTION:
XS GIS Cut Line= 3
      2739589.49     10161244.43      2740171.57      10161327.6
      2741105.73     10161503.12
#Sta/Elev= 30
    4412 1455.59  4582.2 1455.12  4761.7 1451.43  4885.3 1452.41  4894.7 1452.44
  4913.2 1451.06  4930.6 1446.58  4935.7 1446.73  4953.6 1440.37    4963 1435.11
  4963.5 1434.61  4984.7 1435.11  5024.5 1435.24  5053.4 1446.27  5058.5 1445.92
  5065.2 1449.29  5075.4 1450.92  5098.4 1449.68  5248.4  1447.2  5374.4 1448.43
  5441.7 1449.32  5563.8 1453.65  5624.9 1453.75  5651.4 1456.25  5665.6 1456.18
    5704 1463.29  5761.6 1464.63  5777.5 1467.67  5871.7 1476.21  5950.5 1480.12
#Mann= 7 ,-1 , 0
    4412     .05       0  4885.3     .12       0  4894.7     .05       0
    4963     .05       0  4984.7     .05       0  5098.4     .12       0
  5374.4     .05       0
Bank Sta=4963,4984.7
XS Rating Curve= 0 ,0
Exp/Cntr=0.3,0.1

Type RM Length L Ch R = 1 ,98500   ,372,372,372
BEGIN DESCRIPTION:
HICKORY CREEK 197.0
END DESCRIPTION:
XS GIS Cut Line= 3
      2739755.69     10161453.12      2740085.06     10161814.41
      2740905.65     10161703.12
#Sta/Elev= 30
  4511.1 1455.93  4624.3 1454.16  4638.5 1452.49  4723.6 1449.75  4787.1 1450.61
  4815.5 1447.77  4882.7 1444.68  4882.9 1444.67    4929 1440.42  4943.2 1437.62
  4949.9 1434.18  4960.3 1432.57  4960.8 1432.07    4982 1432.57  5010.7 1432.75
    5041 1441.35  5046.5 1445.09  5051.5 1444.04  5061.2 1447.39  5071.3 1448.65
  5194.7 1448.21  5224.1 1447.87  5283.2 1449.49  5353.8 1447.27  5505.2 1458.61
  5569.3 1460.34  5575.8 1462.17  5636.4 1464.52    5707  1463.9  5828.1 1471.09
#Mann= 7 ,-1 , 0
  4511.1     .05       0  4882.7     .12       0  4882.9     .05       0
  4960.3     .05       0    4982     .05       0  5194.7     .12       0
  5224.1     .05       0
Bank Sta=4960.3,4982
XS Rating Curve= 0 ,0
Exp/Cntr=0.3,0.1

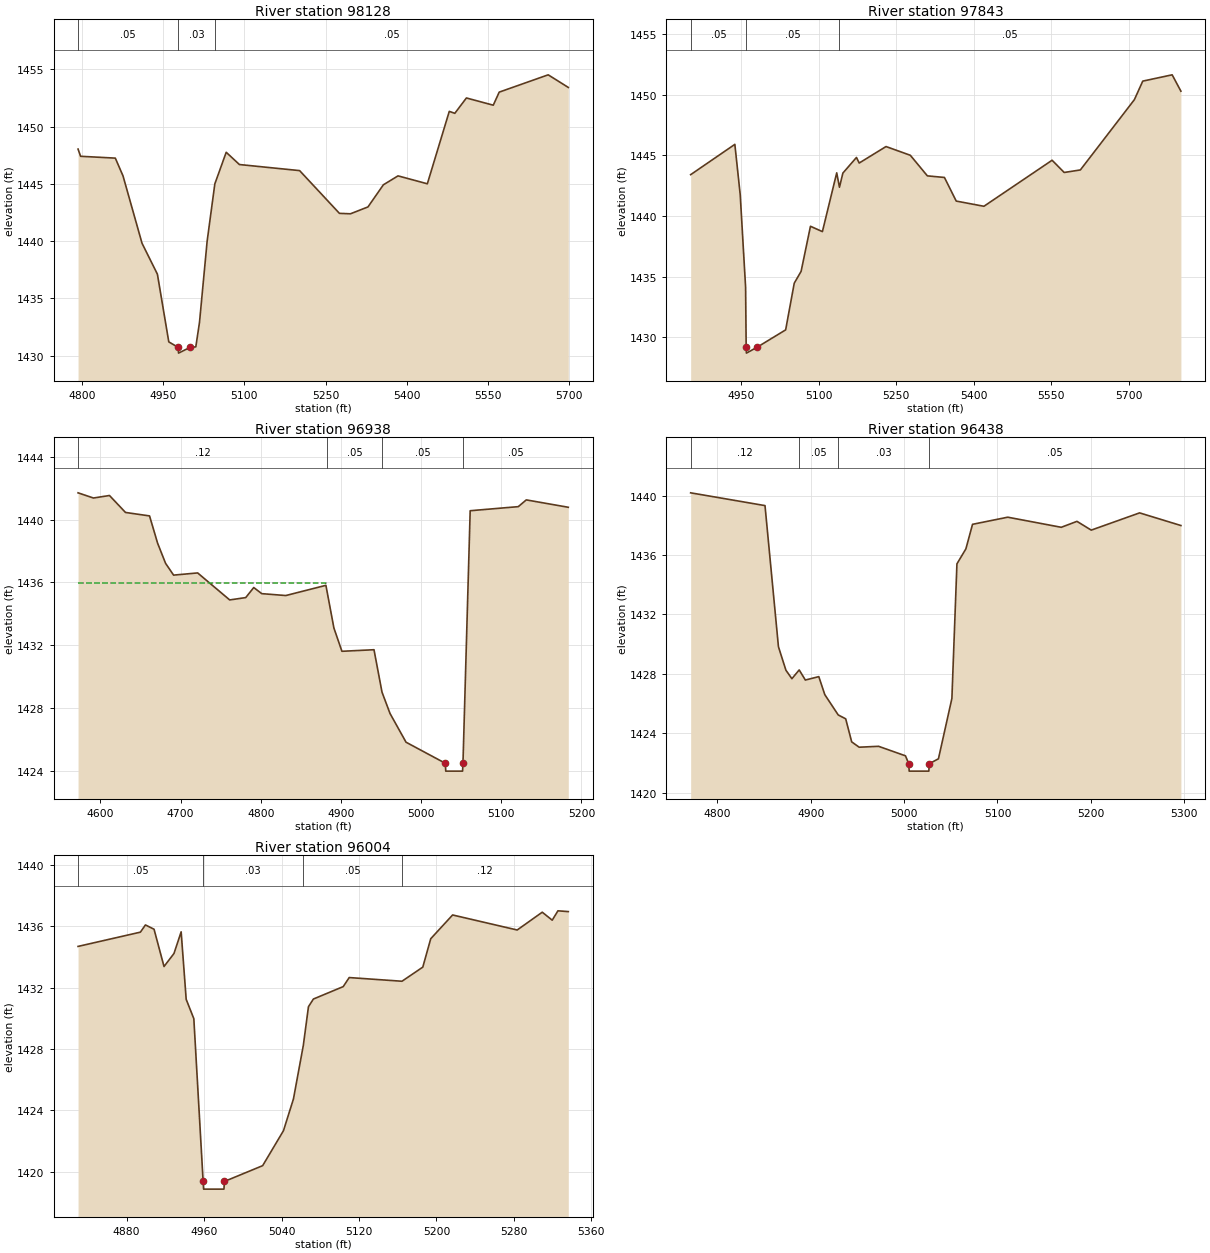
Type RM Length L Ch R = 1 ,98128   ,285,285,285
BEGIN DESCRIPTION:
Mapping XS 6b26a055
END DESCRIPTION:
XS GIS Cut Line= 3
      2739714.72     10161967.21      2739933.59     10162169.25
      2740532.31     10162269.97
#Sta/Elev= 30
  4793.1 1448.03  4797.8  1447.4  4861.9 1447.24  4876.1 1445.69  4911.2 1439.81
  4939.6 1437.11  4960.6  1431.2  4978.1 1430.72  4978.6 1430.22  4999.8 1430.72
  5010.5 1430.77  5017.3 1432.91  5031.4 1439.99  5045.6 1444.99  5066.6 1447.75
    5091 1446.68  5202.1 1446.15  5275.6 1442.42  5295.9 1442.38  5328.3 1442.98
  5356.7 1444.91  5383.8 1445.69  5437.9    1445  5478.4 1451.32  5488.6 1451.15
    5510 1452.49  5559.6 1451.86  5570.6    1453    5661 1454.51  5698.1 1453.41
#Mann= 3 ,-1 , 0
  4793.1     .05       0  4978.1     .03       0  5045.6     .05       0
Bank Sta=4978.1,4999.8
XS Rating Curve= 0 ,0
Exp/Cntr=0.3,0.1

Type RM Length L Ch R = 1 ,97843   ,905,905,905
BEGIN DESCRIPTION:
Mapping XS f7c8ccd3
END DESCRIPTION:
XS GIS Cut Line= 3
      2739523.99     10162264.66      2739725.96     10162326.37
      2740431.87     10162539.27
#Sta/Elev= 30
  4852.2 1443.41  4937.7 1445.91  4948.1 1441.75  4958.5 1434.12  4959.6 1429.18
  4960.1 1428.68  4981.3 1429.18    5036  1430.6  5052.6 1434.45  5065.9 1435.43
    5084 1439.15  5107.1 1438.71  5134.8 1443.56  5140.1 1442.37  5146.7 1443.54
    5173 1444.83  5178.3 1444.37  5230.2 1445.73  5277.2 1445.01  5310.2 1443.31
  5343.2 1443.18    5366 1441.23  5419.6  1440.8  5551.5  1444.6  5574.9 1443.59
  5606.2  1443.8  5710.7  1449.6  5726.9 1451.13  5783.8 1451.65  5800.7  1450.3
#Mann= 3 ,-1 , 0
  4852.2     .05       0  4959.6     .05       0  5140.1     .05       0
Bank Sta=4959.6,4981.3
XS Rating Curve= 0 ,0
Exp/Cntr=0.3,0.1

Type RM Length L Ch R = 1 ,96938   ,500,500,500
BEGIN DESCRIPTION:
Mapping XS 82efd7a3
END DESCRIPTION:
XS GIS Cut Line= 2
       2739776.5     10162859.47      2740388.08     10162865.08
#Sta/Elev= 30
    4572  1441.7  4591.2 1441.37  4611.2 1441.53  4631.2 1440.45  4661.2 1440.23
  4671.2  1438.5  4681.2 1437.21  4691.2 1436.46  4721.2  1436.6  4761.2 1434.88
  4781.2 1435.03  4791.2 1435.67  4801.2 1435.28  4831.2 1435.16  4881.2 1435.81
  4882.9 1435.35  4891.2 1433.09  4901.2 1431.61  4941.2 1431.71  4951.2 1429.01
  4961.2 1427.65  4981.2 1425.82  5030.2 1424.48  5030.7 1423.98  5051.7 1423.98
  5052.2 1424.48  5061.2 1440.56  5121.2 1440.82  5131.2 1441.25  5183.6 1440.78
#Mann= 4 ,-1 , 0
    4572     .12       0  4882.9     .05       0  4951.2     .05       0
  5052.2     .05       0
#XS Ineff= 2 , 0
         4881.24 1435.98
Permanent Ineff=
       F       F
Bank Sta=5030.2,5052.2
XS Rating Curve= 0 ,0
Exp/Cntr=0.3,0.1

Type RM Length L Ch R = 1 ,96438   ,434,434,434
BEGIN DESCRIPTION:
Mapping XS 3b795adc
END DESCRIPTION:
XS GIS Cut Line= 3
      2739714.71     10163061.47       2739939.2     10163241.06
      2740151.55     10163347.24
#Sta/Elev= 30
  4771.5 1440.18  4851.1 1439.32  4865.5 1429.82  4873.5 1428.24  4879.9 1427.67
  4887.7 1428.26  4894.3 1427.58  4908.7 1427.81  4915.1  1426.6  4929.5 1425.23
  4937.5 1424.97  4943.9 1423.42  4951.9 1423.06  4972.7 1423.12  5001.5 1422.48
    5005 1421.95  5005.5 1421.45  5026.5 1421.45    5027 1421.95  5036.8 1422.28
  5051.2 1426.34  5056.6  1435.4  5066.2 1436.41  5073.3 1438.06    5111 1438.54
  5168.3 1437.86  5185.1 1438.26  5200.4 1437.67  5252.2 1438.83  5296.4 1437.98
#Mann= 4 ,-1 , 0
  4771.5     .12       0  4887.7     .05       0  4929.5     .03       0
  5026.5     .05       0
Bank Sta=5005,5027
XS Rating Curve= 0 ,0
Exp/Cntr=0.3,0.1

Type RM Length L Ch R = 1 ,96004   ,504,504,504
BEGIN DESCRIPTION:
Mapping XS d176028a
END DESCRIPTION:
XS GIS Cut Line= 2
       2739619.3     10163583.37      2740111.87     10163465.83
#Sta/Elev= 30
  4829.8 1434.68  4894.2 1435.61  4899.4 1436.08  4908.3  1435.8  4918.6 1433.37
  4928.9 1434.22  4936.3 1435.63  4941.5 1431.23  4949.4 1429.97    4959 1419.36
  4959.5 1418.86  4980.5 1418.86    4981 1419.36  5020.5 1420.39    5042 1422.67
  5052.3 1424.74  5062.5 1428.23  5067.8 1430.75  5072.9 1431.25  5103.7 1432.06
  5109.9 1432.65  5164.4 1432.41  5185.9 1433.33  5194.1 1435.18  5216.7 1436.73
  5283.4 1435.75  5309.3 1436.91  5319.6 1436.39  5325.5    1437  5336.2 1436.95
#Mann= 4 ,-1 , 0
  4829.8     .05       0    4959     .03       0  5062.5     .05       0
  5164.4     .12       0
Bank Sta=4959,4981
XS Rating Curve= 0 ,0
Exp/Cntr=0.3,0.1