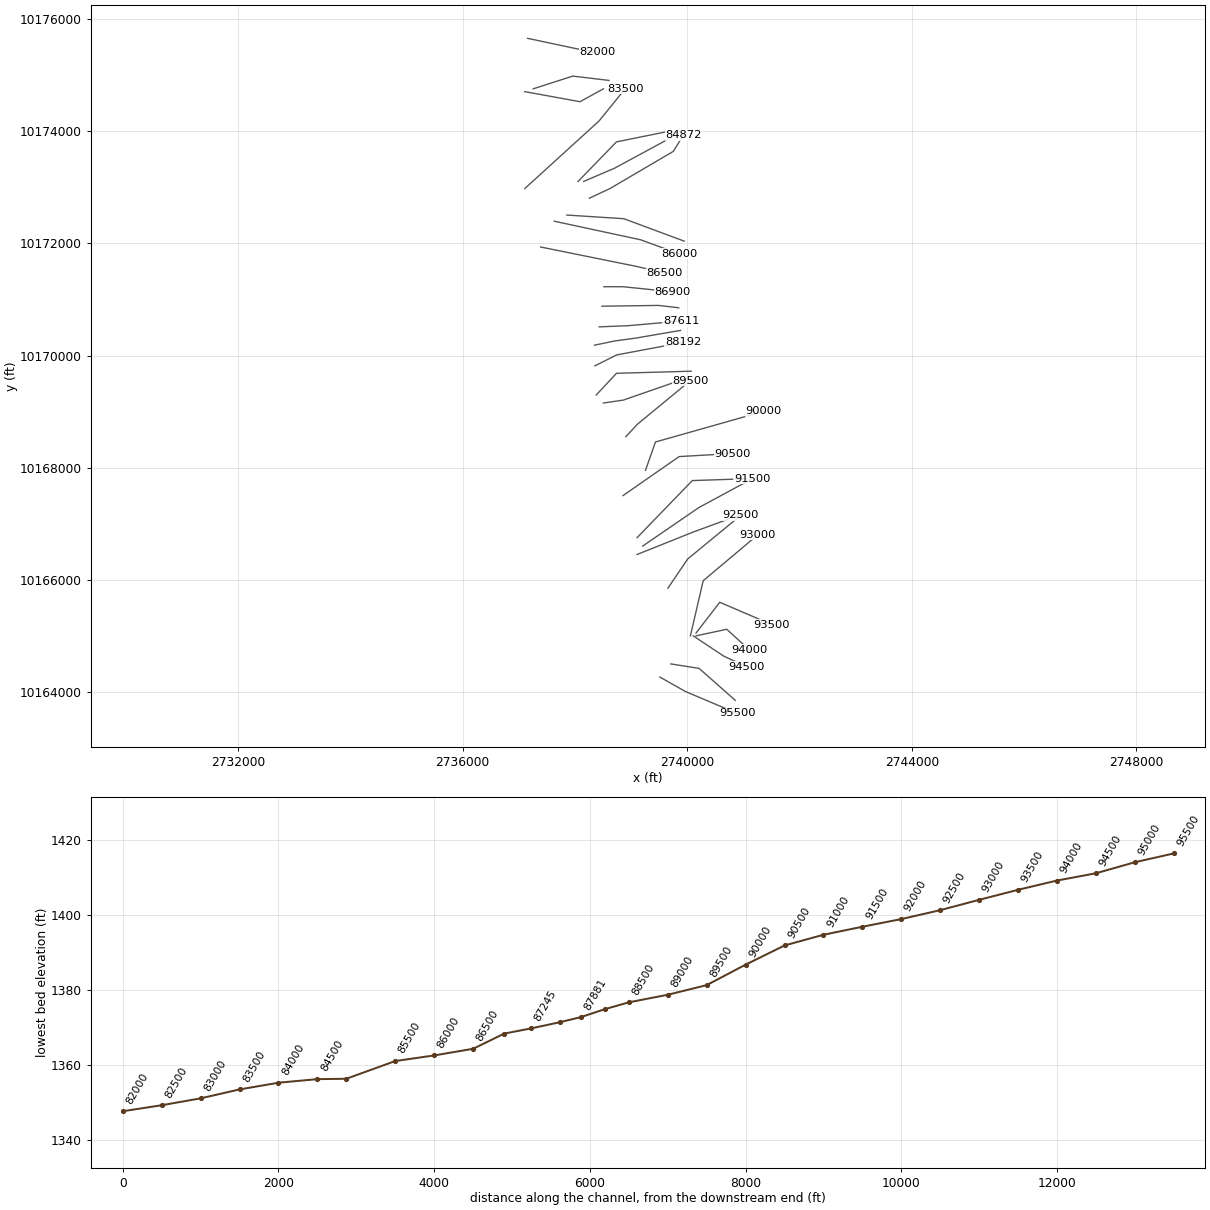
HEC-RAS study HICKORY CREEK.prj: HICKORY CREEK Base Level Engineering

--- HICKORY CREEK.g01 (geometry) --- (continued)

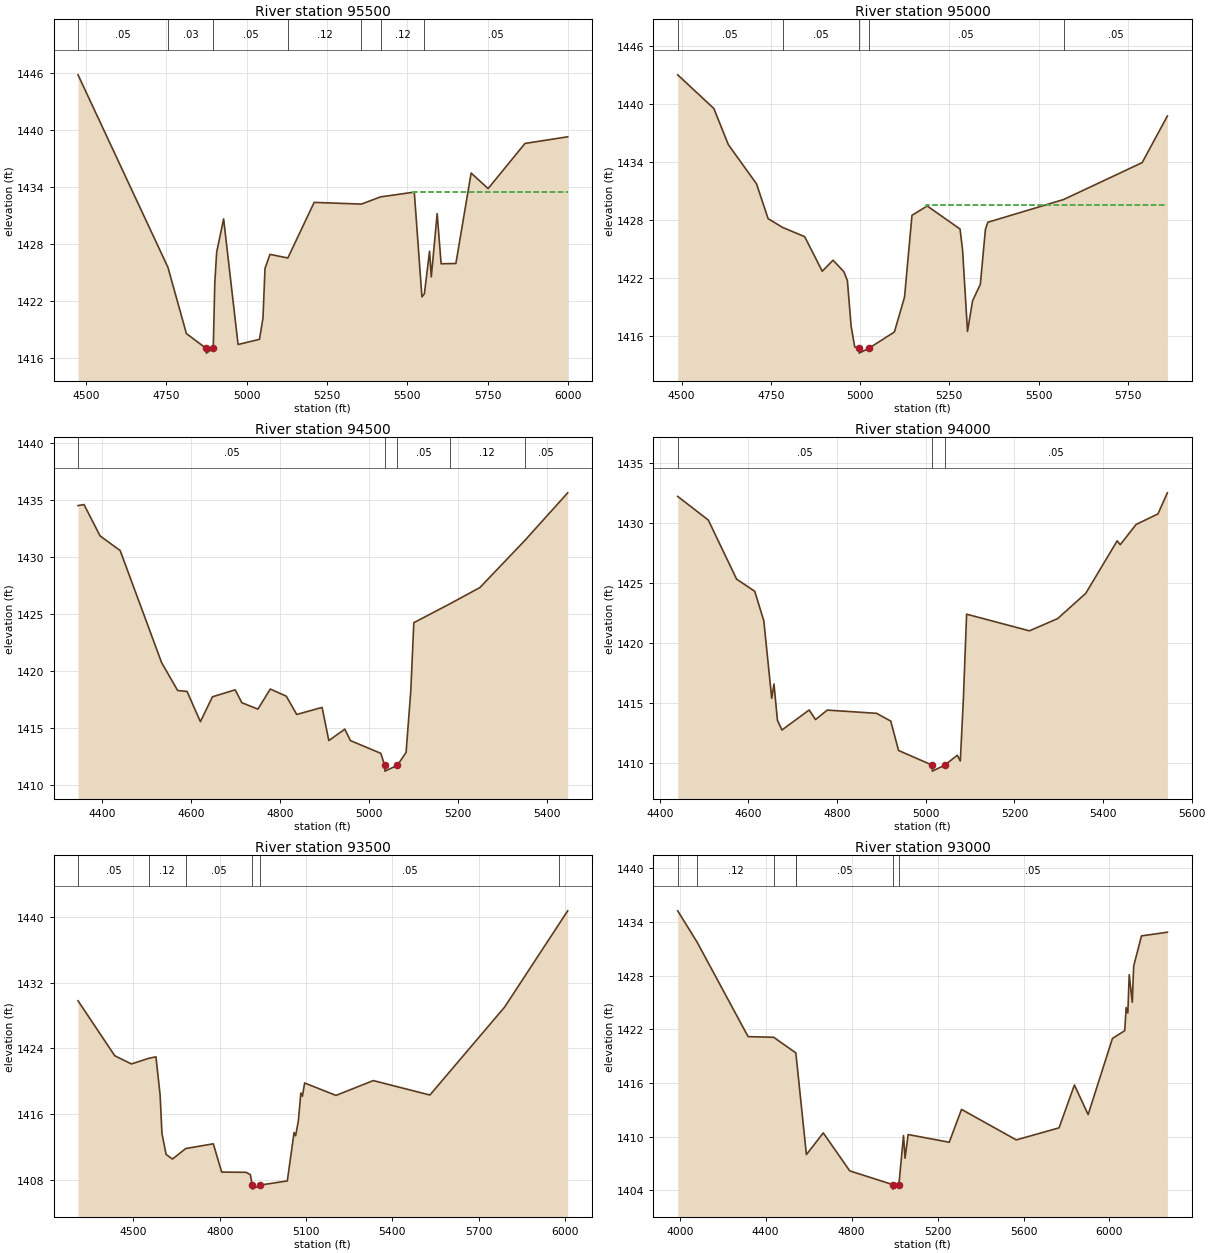
Type RM Length L Ch R = 1 ,95500   ,500,500,500
BEGIN DESCRIPTION:
HICKORY CREEK 191.0
END DESCRIPTION:
XS GIS Cut Line= 3
      2739512.31     10164268.32      2739968.64     10164010.75
      2740887.99     10163621.38
#Sta/Elev= 30
    4476 1445.82  4755.5 1425.57  4812.9  1418.6  4874.4 1417.04  4874.9 1416.54
  4896.4 1417.04  4901.3 1423.96  4907.1 1427.17  4928.7 1430.66  4973.6 1417.45
  5040.2 1417.99  5051.1 1420.25  5057.3 1425.45  5072.8 1426.93  5128.4 1426.55
  5210.2  1432.4  5357.1 1432.22  5416.8 1432.98  5521.5 1433.48  5545.2 1422.46
  5552.9 1422.78  5568.9 1427.26  5574.3 1424.56  5592.6 1431.22  5604.9 1425.94
  5650.8 1425.97  5698.2 1435.49    5751 1433.85  5865.6  1438.6  5998.4  1439.3
#Mann= 7 ,-1 , 0
    4476     .05       0  4755.5     .03       0  4896.4     .05       0
  5128.4     .12       0  5357.1     .05       0  5416.8     .12       0
  5552.9     .05       0
#XS Ineff= 2 , 0
                          5513.3          1433.5
Permanent Ineff=
       F       F
Bank Sta=4874.4,4896.4
XS Rating Curve= 0 ,0
Exp/Cntr=0.3,0.1

Type RM Length L Ch R = 1 ,95000   ,500,500,500
BEGIN DESCRIPTION:
HICKORY CREEK 190.0
END DESCRIPTION:
XS GIS Cut Line= 3
      2739705.63     10164503.12      2740210.46     10164423.29
      2740855.72     10163853.08
#Sta/Elev= 30
  4488.9 1443.03  4590.2 1439.54  4630.7  1435.8  4709.8 1431.73  4742.1 1428.13
  4782.6 1427.22  4844.7 1426.26  4893.9 1422.68  4924.3 1423.82  4954.7 1422.62
  4964.4  1421.7  4974.9 1416.98    4985 1414.83    4997 1414.69  4997.5 1414.19
  5024.4 1414.69  5096.1 1416.38  5124.5 1419.99  5145.4 1428.47  5188.1 1429.44
  5280.1 1427.05  5287.2 1424.86    5301 1416.44  5315.2 1419.61    5337 1421.33
  5351.2 1427.01  5357.9 1427.75  5570.4 1430.11  5790.4 1433.93  5861.1 1438.76
#Mann= 5 ,-1 , 0
  4488.9     .05       0  4782.6     .05       0    4997     .03       0
  5024.4     .05       0  5570.4     .05       0
#XS Ineff= 2 , 0
                         5183.97         1429.58
Permanent Ineff=
       F       F
Bank Sta=4997,5024.4
XS Rating Curve= 0 ,0
Exp/Cntr=0.3,0.1

Type RM Length L Ch R = 1 ,94500   ,500,500,500
BEGIN DESCRIPTION:
HICKORY CREEK 189.0
END DESCRIPTION:
XS GIS Cut Line= 3
      2740105.66     10165003.12      2740650.89     10164640.86
      2741055.67     10164453.12
#Sta/Elev= 30
  4345.4 1434.53  4358.9 1434.62    4395 1431.87  4440.1 1430.59  4533.3 1420.76
  4569.4 1418.31  4590.5 1418.23  4620.5 1415.58  4647.6 1417.76  4698.7 1418.37
  4713.7 1417.24  4749.8 1416.68  4777.6 1418.44  4813.7 1417.81    4837 1416.21
  4894.1 1416.83  4909.2 1413.92  4945.2 1414.92  4957.7 1413.92  5026.1  1412.8
  5034.8 1411.74  5035.3 1411.24  5063.1 1411.74  5082.9 1412.88  5093.5 1418.28
  5100.3 1424.26  5180.7  1425.9  5248.8 1427.34  5349.6 1431.46  5446.2 1435.65
#Mann= 5 ,-1 , 0
  4345.4     .05       0  5034.8     .05       0  5063.1     .05       0
  5180.7     .12       0  5349.6     .05       0
Bank Sta=5034.8,5063.1
XS Rating Curve= 0 ,0
Exp/Cntr=0.3,0.1

Type RM Length L Ch R = 1 ,94000   ,500,500,500
BEGIN DESCRIPTION:
HICKORY CREEK 188.0
END DESCRIPTION:
XS GIS Cut Line= 3
      2740155.71     10165003.12      2740702.86     10165120.49
      2741105.69     10164753.11
#Sta/Elev= 30
  4440.4 1432.21  4509.4 1430.24  4573.3 1425.31  4614.2  1424.3  4634.7 1421.83
  4652.5 1415.37  4657.6 1416.57  4665.4 1413.54  4675.6 1412.73    4737  1414.4
  4751.3  1413.6  4777.9 1414.39  4889.3 1414.12  4921.1 1413.47  4938.7 1411.02
  5014.5  1409.8    5015  1409.3  5042.8  1409.8  5071.2 1410.62    5078 1410.14
    5085 1415.37  5092.2 1422.39  5233.9    1421  5297.6 1422.02  5361.1 1424.13
    5432 1428.51  5438.8 1428.18  5474.6 1429.87  5523.9 1430.75  5545.2 1432.51
#Mann= 3 ,-1 , 0
  4440.4     .05       0  5014.5     .03       0  5042.8     .05       0
Bank Sta=5014.5,5042.8
XS Rating Curve= 0 ,0
Exp/Cntr=0.3,0.1

Type RM Length L Ch R = 1 ,93500   ,500,500,500
BEGIN DESCRIPTION:
HICKORY CREEK 187.0
END DESCRIPTION:
XS GIS Cut Line= 3
      2740155.68     10165053.11      2740578.28     10165601.71
      2741505.65     10165203.13
#Sta/Elev= 30
  4307.5 1429.81  4435.2  1423.1  4493.2  1422.1  4553.5 1422.79  4578.4 1422.97
  4592.9 1418.28  4599.2 1413.62  4613.7 1411.06  4635.7  1410.5  4681.8 1411.78
  4777.7 1412.36  4806.7 1408.91  4891.9 1408.88  4906.4  1408.6    4913 1407.33
  4913.5 1406.83  4941.3 1407.33  5034.9 1407.83  5058.4 1413.74  5063.8 1413.34
  5073.4 1415.18    5082 1418.56  5087.4 1418.16  5095.1 1419.78    5204 1418.26
  5333.7 1420.07  5530.5 1418.31  5790.2 1429.04  5978.8 1439.14  6009.4 1440.78
#Mann= 6 ,-1 , 0
  4307.5     .05       0  4553.5     .12       0  4681.8     .05       0
    4913     .03       0  4941.3     .05       0  5978.8     .12       0
Bank Sta=4913,4941.3
XS Rating Curve= 0 ,0
Exp/Cntr=0.3,0.1

Type RM Length L Ch R = 1 ,93000   ,500,500,500
BEGIN DESCRIPTION:
HICKORY CREEK 186.0
END DESCRIPTION:
XS GIS Cut Line= 3
      2740055.68      10165003.1       2740283.8     10165986.29
      2741255.72     10166803.14
#Sta/Elev= 30
  3990.7 1435.25  4081.2 1431.74  4318.3 1421.19  4437.3 1421.12  4539.2  1419.4
  4540.6 1419.35  4589.6 1408.01  4668.2 1410.43  4791.4 1406.19  4991.8 1404.65
  4992.3 1404.15  5020.1 1404.65  5041.6 1410.14  5048.8 1407.61  5063.1 1410.25
  5254.4 1409.39  5311.6 1413.06  5566.5 1409.65  5765.5    1411    5837 1415.79
  5900.8 1412.48    6014 1420.99  6071.2 1421.86  6077.7 1424.44  6085.5 1423.83
    6092 1428.11  6106.3 1425.03  6112.8 1429.08  6149.2 1432.45  6269.6 1432.86
#Mann= 7 ,-1 , 0
  3990.7     .05       0  4081.2     .12       0  4437.3     .05       0
  4539.2     .12       0  4540.6     .05       0  4991.8     .03       0
  5020.1     .05       0
Bank Sta=4991.8,5020.1
XS Rating Curve= 0 ,0
Exp/Cntr=0.3,0.1

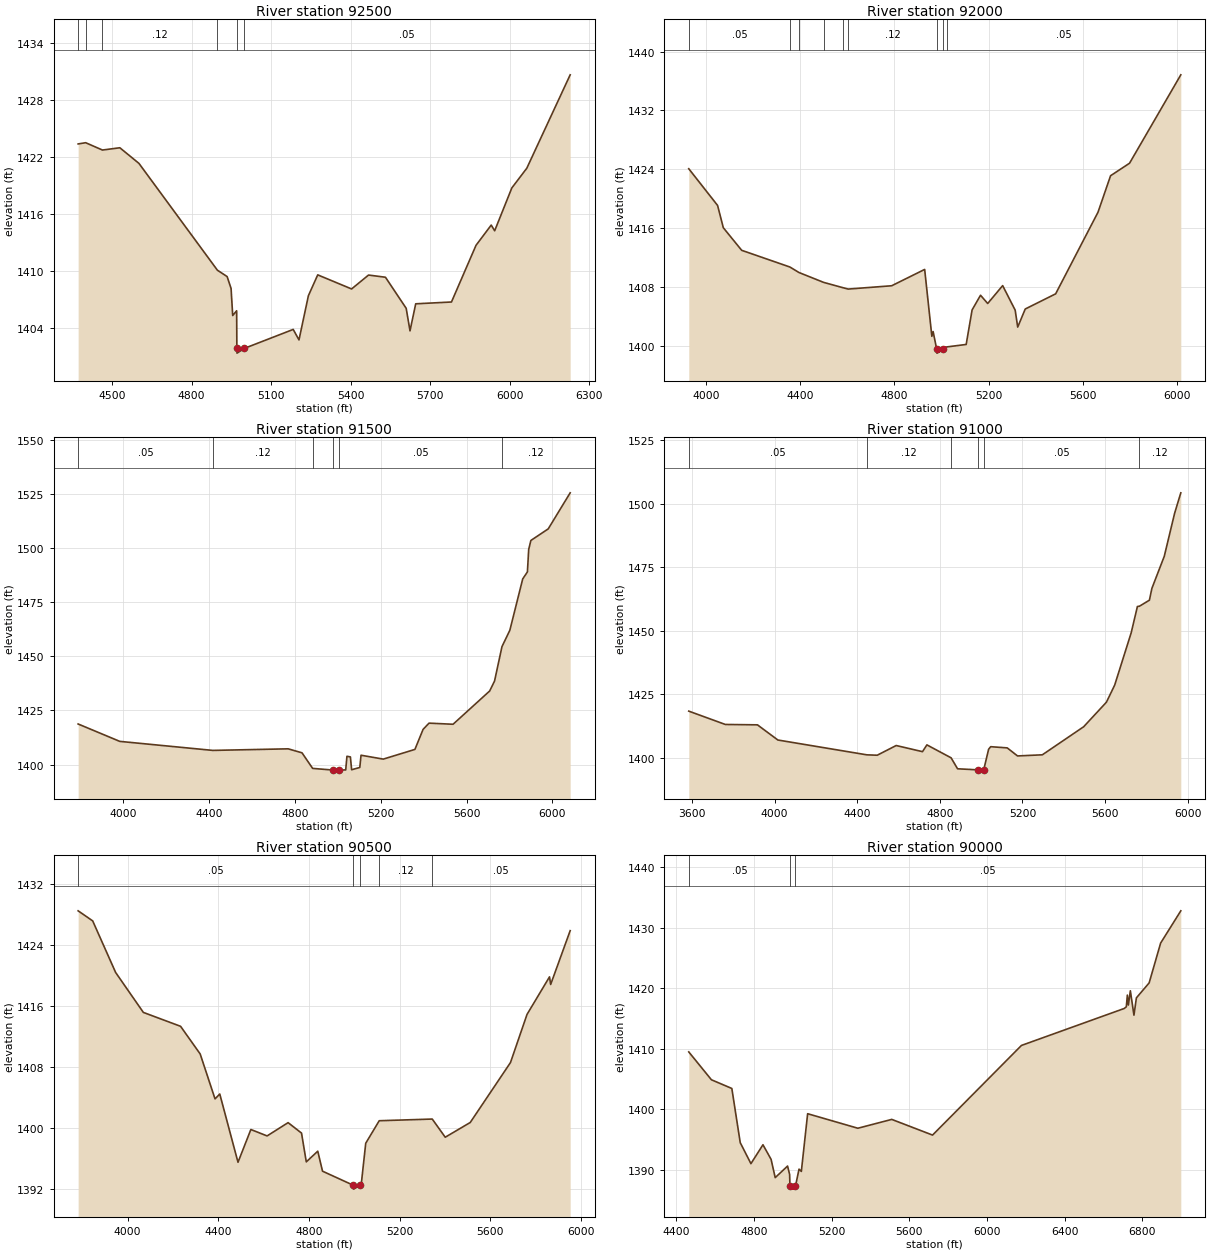
Type RM Length L Ch R = 1 ,92500   ,500,500,500
BEGIN DESCRIPTION:
HICKORY CREEK 185.0
END DESCRIPTION:
XS GIS Cut Line= 3
      2739655.69     10165853.12      2740007.39      10166373.4
       2740955.7     10167153.12
#Sta/Elev= 30
    4372 1423.36  4400.4 1423.49  4463.7 1422.72  4529.3 1422.96  4601.3 1421.32
  4897.2  1410.1  4933.9 1409.43  4948.8 1408.18  4954.9 1405.34  4969.8 1405.84
  4970.6 1401.89  4971.1 1401.39    4999 1401.89  5183.1 1403.88  5204.9 1402.78
  5240.4 1407.42  5275.6 1409.61  5403.3 1408.13  5467.2 1409.59    5531 1409.36
  5609.2  1406.1  5623.6 1403.73  5645.1 1406.57    5780 1406.76  5872.5 1412.71
  5929.9 1414.84  5942.9 1414.24  6007.6 1418.74  6064.1 1420.81  6227.7 1430.62
#Mann= 6 ,-1 , 0
    4372     .12       0  4400.4     .05       0  4463.7     .12       0
  4897.2     .05       0  4970.6     .03       0    4999     .05       0
Bank Sta=4970.6,4999
XS Rating Curve= 0 ,0
Exp/Cntr=0.3,0.1

Type RM Length L Ch R = 1 ,92000   ,500,500,500
BEGIN DESCRIPTION:
HICKORY CREEK 184.0
END DESCRIPTION:
XS GIS Cut Line= 3
      2739105.71     10166453.12      2740102.11     10166852.07
      2741055.65      10167203.1
#Sta/Elev= 30
  3926.7 1424.08  4049.1 1419.09  4073.4 1416.06  4151.4 1412.99    4356 1410.72
  4394.7 1409.97  4499.2 1408.63  4582.2  1407.9  4603.7 1407.72  4788.4 1408.17
  4928.4 1410.39  4958.9  1401.3  4964.3 1401.94  4979.7 1399.51  4980.2 1399.01
  5008.1 1399.51  5021.6 1399.85  5104.7 1400.19  5129.8 1404.88  5165.6 1406.88
  5196.1 1405.76  5259.6 1408.19  5312.8 1404.85  5323.5 1402.55  5355.5 1405.01
  5484.6 1407.07  5664.5 1418.17  5717.8 1423.13  5798.4 1424.83  6016.1 1436.85
#Mann= 9 ,-1 , 0
  3926.7     .05       0    4356     .12       0  4394.7     .05       0
  4499.2     .12       0  4582.2     .05       0  4603.7     .12       0
  4979.7     .07       0  5008.1     .12       0  5021.6     .05       0
Bank Sta=4979.7,5008.1
XS Rating Curve= 0 ,0
Exp/Cntr=0.3,0.1

Type RM Length L Ch R = 1 ,91500   ,500,500,500
BEGIN DESCRIPTION:
HICKORY CREEK 183.0
END DESCRIPTION:
XS GIS Cut Line= 3
       2739205.7     10166603.12      2740203.08     10167287.67
      2741155.67      10167803.1
#Sta/Elev= 30
  3790.3 1418.73  3984.3  1410.7  4417.9 1406.53  4768.9 1407.26  4833.4 1405.42
    4883 1398.22  4976.8 1397.46  4977.3 1396.96  5005.2 1397.46  5037.1 1397.51
  5042.9 1403.82    5059 1403.52  5064.7  1397.6  5102.8 1398.65  5108.5  1404.3
  5212.2 1402.51  5359.6 1406.99  5397.7 1416.25  5425.3 1419.12  5537.4 1418.61
  5707.9 1433.97  5730.6 1438.55  5765.3 1454.47    5802 1462.04  5861.9 1485.74
  5883.8 1488.97  5889.8 1499.38    5900  1503.5  5980.8 1508.85  6083.1  1525.5
#Mann= 6 ,-1 , 0
  3790.3     .05       0  4417.9     .12       0    4883     .05       0
  4976.8     .03       0  5005.2     .05       0  5765.3     .12       0
Bank Sta=4976.8,5005.2
XS Rating Curve= 0 ,0
Exp/Cntr=0.3,0.1

Type RM Length L Ch R = 1 ,91000   ,500,500,500
BEGIN DESCRIPTION:
HICKORY CREEK 182.0
END DESCRIPTION:
XS GIS Cut Line= 3
      2739105.67      10166753.1      2740089.65     10167770.66
      2741055.71     10167803.11
#Sta/Elev= 30
  3584.5 1418.44  3761.4 1413.19    3917 1413.04  4015.8 1407.07  4446.8 1401.23
  4496.8 1401.08  4588.7  1404.9    4716 1402.48  4737.4 1405.15  4854.5 1400.06
  4885.8 1395.74    4984 1395.32  4984.5 1394.82  5012.4 1395.32  5036.1 1403.42
  5046.1 1404.44  5126.1 1403.97  5176.1  1400.8  5296.2 1401.24  5496.3 1412.29
  5606.4 1421.95  5646.4 1428.67  5726.4 1449.29  5756.5 1459.63  5766.4 1459.75
  5814.6 1462.11  5826.5 1466.74  5886.5 1479.39  5936.6 1496.33  5966.6 1504.38
#Mann= 6 ,-1 , 0
  3584.5     .05       0  4446.8     .12       0  4854.5     .05       0
    4984     .03       0  5012.4     .05       0  5766.4     .12       0
Bank Sta=4984,5012.4
XS Rating Curve= 0 ,0
Exp/Cntr=0.3,0.1

Type RM Length L Ch R = 1 ,90500   ,500,500,500
BEGIN DESCRIPTION:
HICKORY CREEK 181.0
END DESCRIPTION:
XS GIS Cut Line= 3
      2738855.68     10167503.11      2739855.44     10168198.45
      2740805.67     10168253.11
#Sta/Elev= 30
  3782.2 1428.42  3846.4  1427.1  3947.6 1420.34  4069.8 1415.11  4233.9 1413.29
  4320.3 1409.67  4385.8 1403.78  4406.7 1404.42  4487.1 1395.48  4543.8 1399.77
  4615.4 1398.93    4708 1400.67  4767.2  1399.3  4788.2 1395.53  4838.8 1396.93
  4859.8 1394.31  4996.1 1392.46  4996.6 1391.96  5024.5 1392.46  5030.3 1392.53
  5050.3 1397.97  5109.8 1400.92  5343.6 1401.14  5400.9 1398.76  5511.1 1400.69
  5688.5 1408.54  5761.5 1414.85  5860.7 1419.77  5865.7 1418.77  5951.8 1425.82
#Mann= 5 ,-1 , 0
  3782.2     .05       0  4996.1     .03       0  5024.5     .05       0
  5109.8     .12       0  5343.6     .05       0
Bank Sta=4996.1,5024.5
XS Rating Curve= 0 ,0
Exp/Cntr=0.3,0.1

Type RM Length L Ch R = 1 ,90000   ,500,500,500
BEGIN DESCRIPTION:
HICKORY CREEK 180.0
END DESCRIPTION:
XS GIS Cut Line= 3
      2739255.69     10167953.12      2739433.09     10168458.28
      2741355.68     10169003.11
#Sta/Elev= 30
  4464.6 1409.51  4581.2 1404.91  4686.4 1403.47  4729.6 1394.52  4784.7 1391.05
  4846.6 1394.17  4888.5 1391.76  4909.7 1388.74  4973.3 1390.65  4983.9 1389.28
  4985.7 1387.34  4986.2 1386.84  5014.1 1387.34  5032.4 1390.14  5044.3 1389.77
  5076.7  1399.3  5335.3  1396.9  5509.8 1398.36  5719.9 1395.77  6177.7 1410.58
  6707.3 1416.69  6717.7 1416.97    6723  1418.9  6728.2 1417.25  6738.5 1419.61
    6757 1415.58  6769.6 1418.44  6835.2 1420.91  6894.4 1427.49  6998.3 1432.82
#Mann= 3 ,-1 , 0
  4464.6     .05       0  4985.7     .05       0  5014.1     .05       0
Bank Sta=4985.7,5014.1
XS Rating Curve= 0 ,0
Exp/Cntr=0.3,0.1

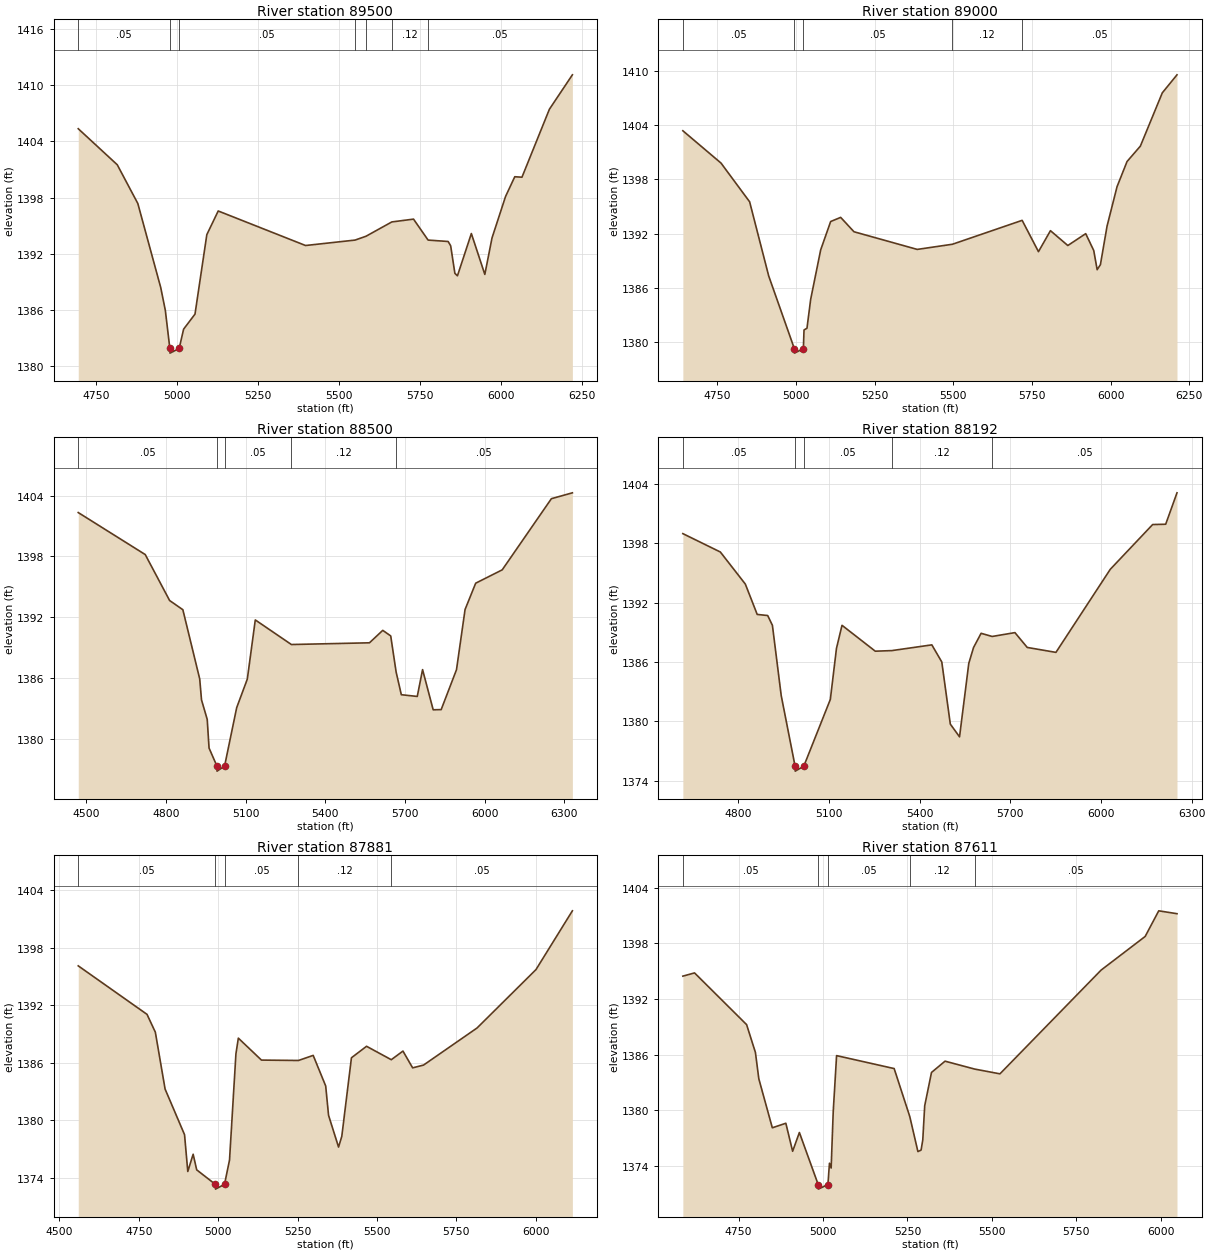
Type RM Length L Ch R = 1 ,89500   ,500,500,500
BEGIN DESCRIPTION:
HICKORY CREEK 179.0
END DESCRIPTION:
XS GIS Cut Line= 3
      2738905.66     10168553.09      2739114.06      10168776.6
      2740055.68     10169553.11
#Sta/Elev= 30
  4694.4 1405.35  4814.9  1401.5  4878.4 1397.36  4949.2 1388.37  4963.4 1385.93
  4977.3 1381.87  4977.8 1381.37  5006.1 1381.87  5019.8 1383.93    5055 1385.54
  5091.5 1394.03  5126.7 1396.56  5396.4 1392.87  5549.4 1393.45  5583.1 1393.86
  5662.9 1395.39  5729.9 1395.69  5774.9 1393.45  5836.8  1393.3  5844.6 1392.84
  5857.6  1389.9  5865.5 1389.63  5908.5 1394.15  5950.1 1389.78  5972.3 1393.68
    6014  1398.1  6042.6 1400.22  6064.8 1400.17  6149.5 1407.43  6220.5 1411.11
#Mann= 7 ,-1 , 0
  4694.4     .05       0  4977.3     .03       0  5006.1     .05       0
  5549.4     .12       0  5583.1     .05       0  5662.9     .12       0
  5774.9     .05       0
Bank Sta=4977.3,5006.1
XS Rating Curve= 0 ,0
Exp/Cntr=0.3,0.1

Type RM Length L Ch R = 1 ,89000   ,500,500,500
BEGIN DESCRIPTION:
HICKORY CREEK 178.0
END DESCRIPTION:
XS GIS Cut Line= 3
      2738505.66     10169153.11      2738861.84     10169205.42
      2740005.68     10169603.11
#Sta/Elev= 30
    4640 1403.37  4761.3  1399.8  4852.3 1395.52  4912.9 1387.33  4994.4  1379.3
  4994.9  1378.8  5023.2  1379.3  5025.2 1381.36  5034.6 1381.55  5046.4 1384.75
  5078.2 1390.21  5109.9 1393.34  5141.7  1393.8  5184.1 1392.21  5385.2 1390.26
  5497.1 1390.83  5718.7 1393.47  5770.6 1390.01  5808.7 1392.33  5863.9 1390.69
  5920.8    1392  5946.3 1390.14  5957.2 1388.02  5967.5 1388.57  5988.7 1392.84
  6020.4 1397.19  6052.2 1399.97  6094.5 1401.67  6164.3 1407.56    6211 1409.55
#Mann= 5 ,-1 , 0
    4640     .05       0  4994.4     .05       0  5023.2     .05       0
  5497.1     .12       0  5718.7     .05       0
Bank Sta=4994.4,5023.2
XS Rating Curve= 0 ,0
Exp/Cntr=0.3,0.1

Type RM Length L Ch R = 1 ,88500   ,308,308,308
BEGIN DESCRIPTION:
HICKORY CREEK 177.0
END DESCRIPTION:
XS GIS Cut Line= 3
      2738377.12       10169295.      2738739.67     10169682.84
      2740069.84     10169720.34
#Sta/Elev= 30
  4469.1 1402.33  4721.5 1398.18  4813.3 1393.64  4863.2 1392.73  4926.7 1385.89
  4933.5 1383.82    4955 1381.89  4961.9 1379.06  4991.6 1377.28  4992.1 1376.78
  5020.4 1377.28    5066 1383.05  5106.1 1385.88  5136.1 1391.72  5272.1 1389.29
  5566.2 1389.46  5616.3 1390.69  5646.3 1390.14  5666.7 1386.57  5686.3 1384.33
  5746.3 1384.16  5766.3 1386.81  5806.3 1382.84  5836.4 1382.86  5894.1  1386.8
  5926.4 1392.75  5966.4 1395.35  6066.4 1396.67  6251.6  1403.7  6330.7 1404.28
#Mann= 5 ,-1 , 0
  4469.1     .05       0  4991.6     .03       0  5020.4     .05       0
  5272.1     .12       0  5666.7     .05       0
Bank Sta=4991.6,5020.4
XS Rating Curve= 0 ,0
Exp/Cntr=0.3,0.1

Type RM Length L Ch R = 1 ,88192   ,311,311,311
BEGIN DESCRIPTION:
Mapping XS 26f53faa
END DESCRIPTION:
XS GIS Cut Line= 3
      2738354.74     10169816.18      2738743.59     10170010.61
      2739922.44     10170232.51
#Sta/Elev= 30
  4617.3 1398.99  4741.3 1397.13    4824 1393.88  4863.2 1390.81  4897.9  1390.7
  4913.5 1389.71  4942.6  1382.6  4988.5 1375.45    4989 1374.95  5017.3 1375.45
  5105.1 1382.21  5125.4 1387.38  5143.7 1389.71  5253.7 1387.09  5308.5 1387.15
  5440.8 1387.73  5473.7    1386  5501.9 1379.71  5532.4 1378.42    5563 1385.86
  5578.7 1387.46  5603.7  1388.9  5640.3 1388.58  5715.6 1388.97  5756.3 1387.47
  5851.2 1386.97    6031 1395.38  6171.1 1399.91  6214.2 1399.94  6251.6 1403.12
#Mann= 5 ,-1 , 0
  4617.3     .05       0  4988.5     .03       0  5017.3     .05       0
  5308.5     .12       0  5640.3     .05       0
Bank Sta=4988.5,5017.3
XS Rating Curve= 0 ,0
Exp/Cntr=0.3,0.1

Type RM Length L Ch R = 1 ,87881   ,270,270,270
BEGIN DESCRIPTION:
Mapping XS 3831bc91
END DESCRIPTION:
XS GIS Cut Line= 4
       2738347.8     10170184.23      2738715.81     10170260.61
      2739076.92     10170309.22      2739881.63     10170447.96
#Sta/Elev= 30
  4559.1  1396.1  4775.8 1391.04    4802 1389.18  4832.7 1383.25    4894 1378.49
  4904.2 1374.65  4921.1 1376.45  4932.3 1374.82    4991 1373.31  4991.5 1372.81
  5019.9 1373.31  5035.7 1375.84  5055.9 1386.93  5063.5 1388.56  5136.3 1386.27
    5253 1386.23  5299.3 1386.76  5338.7 1383.57  5347.7 1380.51  5379.2  1377.2
  5389.4 1378.31  5419.8 1386.51  5467.4 1387.71  5545.3 1386.31  5582.1 1387.21
  5612.6 1385.46    5647 1385.75  5815.6 1389.62  6001.2 1395.71  6115.9 1401.84
#Mann= 5 ,-1 , 0
  4559.1     .05       0    4991     .05       0  5019.9     .05       0
    5253     .12       0  5545.3     .05       0
Bank Sta=4991,5019.9
XS Rating Curve= 0 ,0
Exp/Cntr=0.3,0.1

Type RM Length L Ch R = 1 ,87611   ,366,366,366
BEGIN DESCRIPTION:
Mapping XS 813da09f
END DESCRIPTION:
XS GIS Cut Line= 3
      2738431.09     10170510.61      2738951.92     10170531.44
      2739889.47     10170614.78
#Sta/Elev= 30
  4585.3 1394.47  4619.9 1394.82    4774 1389.23  4800.1 1386.22  4810.1 1383.38
  4850.1 1378.08  4890.1 1378.57  4910.2 1375.54  4930.2 1377.57  4985.8 1371.95
  4986.3 1371.45  5014.7 1371.95  5019.2 1374.25  5024.2 1373.73  5030.3 1379.78
  5040.3 1385.88  5210.7 1384.48  5256.9  1379.3    5281 1375.51  5290.4 1375.67
  5295.4 1376.77  5301.1 1380.46  5321.2 1384.06  5361.3 1385.28  5448.5 1384.43
  5523.8 1383.91  5823.1 1395.12  5953.6 1398.76  5993.8 1401.53  6047.8 1401.22
#Mann= 5 ,-1 , 0
  4585.3     .05       0  4985.8     .05       0  5014.7     .05       0
  5256.9     .12       0  5448.5     .05       0
Bank Sta=4985.8,5014.7
XS Rating Curve= 0 ,0
Exp/Cntr=0.3,0.1

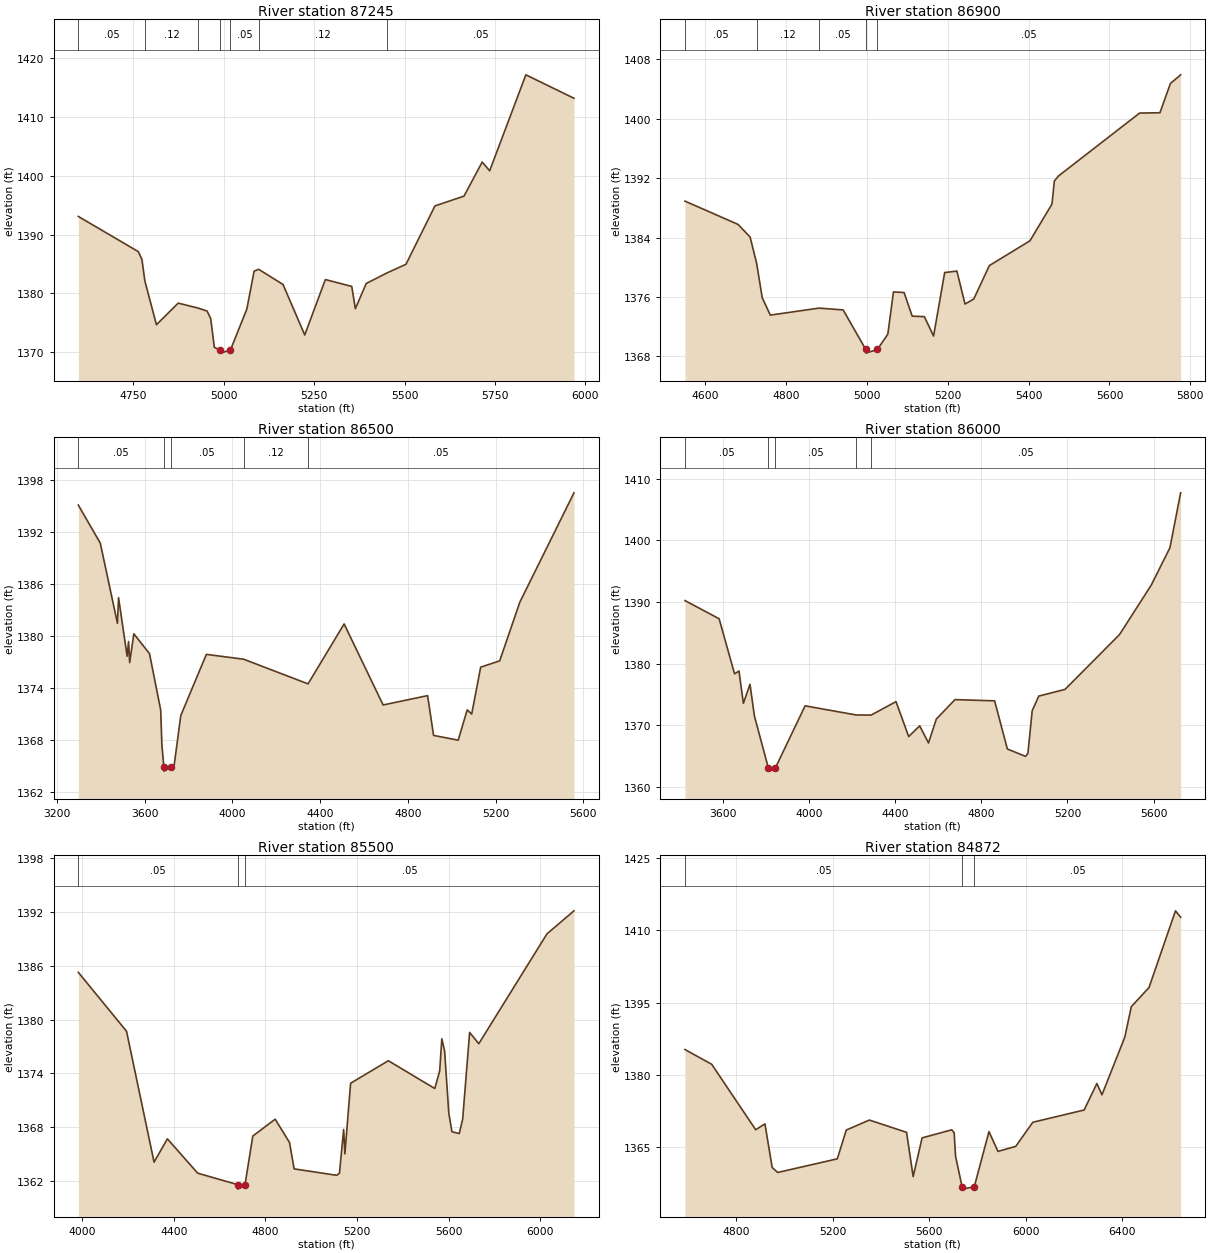
Type RM Length L Ch R = 1 ,87245   ,345,345,345
BEGIN DESCRIPTION:
Mapping XS 9fad360f
END DESCRIPTION:
XS GIS Cut Line= 3
      2738479.66     10170878.66      2739486.65     10170892.55
      2739847.77     10170850.89
#Sta/Elev= 30
    4598 1393.08    4764 1387.09    4774 1385.74  4781.9 1382.13    4814 1374.65
  4874.1 1378.33  4929.2 1377.49  4954.1 1376.98  4964.1 1375.69  4974.1 1370.81
  4989.6 1370.32  4990.1 1369.82  5018.5 1370.32  5064.1 1377.34  5084.1 1383.77
  5096.6 1384.09  5164.1  1381.5  5224.1 1372.91  5281.1 1382.34  5354.1 1381.17
  5364.1 1377.38  5394.1 1381.67  5452.6  1383.5  5504.1 1384.94  5584.1 1394.87
  5664.5 1396.54  5714.8 1402.34  5735.5 1400.85  5835.6 1417.18  5968.6 1413.19
#Mann= 7 ,-1 , 0
    4598     .05       0  4781.9     .12       0  4929.2     .05       0
  4989.6     .05       0  5018.5     .05       0  5096.6     .12       0
  5452.6     .05       0
Bank Sta=4989.6,5018.5
XS Rating Curve= 0 ,0
Exp/Cntr=0.3,0.1

Type RM Length L Ch R = 1 ,86900   ,400,400,400
BEGIN DESCRIPTION:
Mapping XS 614875d0
END DESCRIPTION:
XS GIS Cut Line= 3
      2738514.46     10171225.89       2738854.7     10171225.89
      2739736.65     10171135.61
#Sta/Elev= 30
  4549.4  1388.9  4680.6 1385.77  4710.6 1384.07  4726.8 1380.51  4740.6 1375.89
  4760.6 1373.55    4881 1374.49  4940.9 1374.25  4996.8 1368.93  4997.3 1368.43
  5025.7 1368.93  5051.5 1370.99  5065.4 1376.68  5091.7 1376.59  5111.8 1373.41
  5141.9 1373.34  5164.7 1370.73  5192.2 1379.28  5222.4 1379.48  5242.5 1375.04
  5264.1 1375.71  5302.8 1380.22  5403.3 1383.56  5457.8 1388.51  5463.6 1391.61
  5473.7 1392.28  5674.7 1400.76    5725  1400.8  5750.9 1404.74  5776.2 1405.91
#Mann= 5 ,-1 , 0
  4549.4     .05       0  4726.8     .12       0    4881     .05       0
  4996.8     .03       0  5025.7     .05       0
Bank Sta=4996.8,5025.7
XS Rating Curve= 0 ,0
Exp/Cntr=0.3,0.1

Type RM Length L Ch R = 1 ,86500   ,500,500,500
BEGIN DESCRIPTION:
HICKORY CREEK 173.0
END DESCRIPTION:
XS GIS Cut Line= 3
      2737387.54     10171933.88      2739056.57     10171595.92
      2739600.85     10171473.86
#Sta/Elev= 30
  3297.1 1395.13  3397.2 1390.74  3475.5 1381.47  3480.6 1384.43  3519.7 1377.66
  3526.2 1379.36  3531.3 1376.92  3550.3 1380.25  3621.7 1377.96  3672.7 1371.46
  3678.3 1367.38  3687.2 1364.87  3687.7 1364.37  3719.5 1364.87  3734.1 1365.02
  3764.5  1370.8  3881.1 1377.87  4051.2 1377.31  4344.9 1374.46  4509.4 1381.39
  4687.3 1372.02  4890.1  1373.1  4917.5  1368.5  5029.8 1367.95  5070.8 1371.45
  5091.3 1370.97  5132.3 1376.39    5219 1377.12  5310.8  1383.9  5557.8 1396.55
#Mann= 5 ,-1 , 0
  3297.1     .05       0  3687.2     .03       0  3719.5     .05       0
  4051.2     .12       0  4344.9     .05       0
Bank Sta=3687.2,3719.5
XS Rating Curve= 0 ,0
Exp/Cntr=0.3,0.1

Type RM Length L Ch R = 1 ,86000   ,500,500,500
BEGIN DESCRIPTION:
HICKORY CREEK 172.0
END DESCRIPTION:
XS GIS Cut Line= 3
      2737630.63     10172393.94      2739170.67     10172062.07
      2739851.77     10171812.73
#Sta/Elev= 30
  3424.6 1390.24  3583.2 1387.29  3654.8 1378.36  3675.3 1378.83  3695.7 1373.58
  3726.4 1376.67  3746.9 1371.53  3811.7  1363.1  3812.2  1362.6    3844  1363.1
  3982.2 1373.18  4219.3  1371.7  4288.5 1371.68  4404.2 1373.86    4463  1368.2
  4514.1 1369.94    4555 1367.16  4591.2 1371.03  4677.8 1374.19  4861.9 1373.99
    4921 1366.19  5005.3 1364.99  5016.4 1365.49  5036.3 1372.39  5066.8 1374.76
  5188.9 1375.85  5441.9 1384.74  5589.5 1392.78  5675.7 1398.81  5725.3  1407.7
#Mann= 5 ,-1 , 0
  3424.6     .05       0  3811.7     .03       0    3844     .05       0
  4219.3      .1       0  4288.5     .05       0
Bank Sta=3811.7,3844
XS Rating Curve= 0 ,0
Exp/Cntr=0.3,0.1

Type RM Length L Ch R = 1 ,85500   ,628,628,628
BEGIN DESCRIPTION:
HICKORY CREEK 171.0
END DESCRIPTION:
XS GIS Cut Line= 3
      2737855.72     10172503.11      2738870.15     10172438.24
      2739944.99     10172038.38
#Sta/Elev= 30
  3983.5 1385.28  4193.9 1378.71  4314.1 1364.11  4372.2 1366.71  4504.5 1362.88
  4678.8  1361.6  4679.3  1361.1  4711.1  1361.6    4745 1367.02  4842.7  1368.9
  4905.3  1366.3  4925.4 1363.36  5111.2 1362.64  5123.3 1362.88  5141.5 1367.75
  5146.9 1365.04  5171.9 1372.91  5336.7 1375.42  5539.4 1372.32  5560.7 1374.29
    5570 1377.87  5582.1 1376.53  5600.4  1369.6  5614.1  1367.5  5646.1  1367.3
    5661 1368.91  5691.4 1378.58  5731.4 1377.32  6028.9 1389.57  6146.8 1392.14
#Mann= 3 ,-1 , 0
  3983.5     .05       0  4678.8     .03       0  4711.1     .05       0
Bank Sta=4678.8,4711.1
XS Rating Curve= 0 ,0
Exp/Cntr=0.3,0.1

Type RM Length L Ch R = 1 ,84872   ,372,372,372
BEGIN DESCRIPTION:
HICKORY CREEK 170.0
END DESCRIPTION:
XS GIS Cut Line= 4
      2738255.71     10172803.12       2738629.5       10172979.
      2739751.58      10173638.7      2739930.69     10173928.12
#Sta/Elev= 30
  4586.9 1385.31  4697.7 1382.25  4880.1 1368.68  4918.4  1369.9  4948.5 1360.85
  4971.3 1359.82  5218.5 1362.65  5255.7 1368.61  5351.4 1370.69  5505.7 1368.14
    5533 1358.96  5570.1 1366.99  5693.1 1368.67    5703 1368.05  5708.8 1363.17
  5735.9 1356.87  5736.9 1356.37  5786.5 1356.87  5847.4  1368.3  5884.6 1364.19
  5958.4 1365.24    6029 1370.23  6241.9 1372.77  6294.7 1378.26  6315.8 1375.93
  6410.4 1387.85  6437.5 1394.19  6510.8 1398.15  6620.7 1414.06    6642 1412.74
#Mann= 3 ,-1 , 0
  4586.9     .05       0  5735.9     .03       0  5786.5     .05       0
Bank Sta=5735.9,5786.5
XS Rating Curve= 0 ,0
Exp/Cntr=0.3,0.1

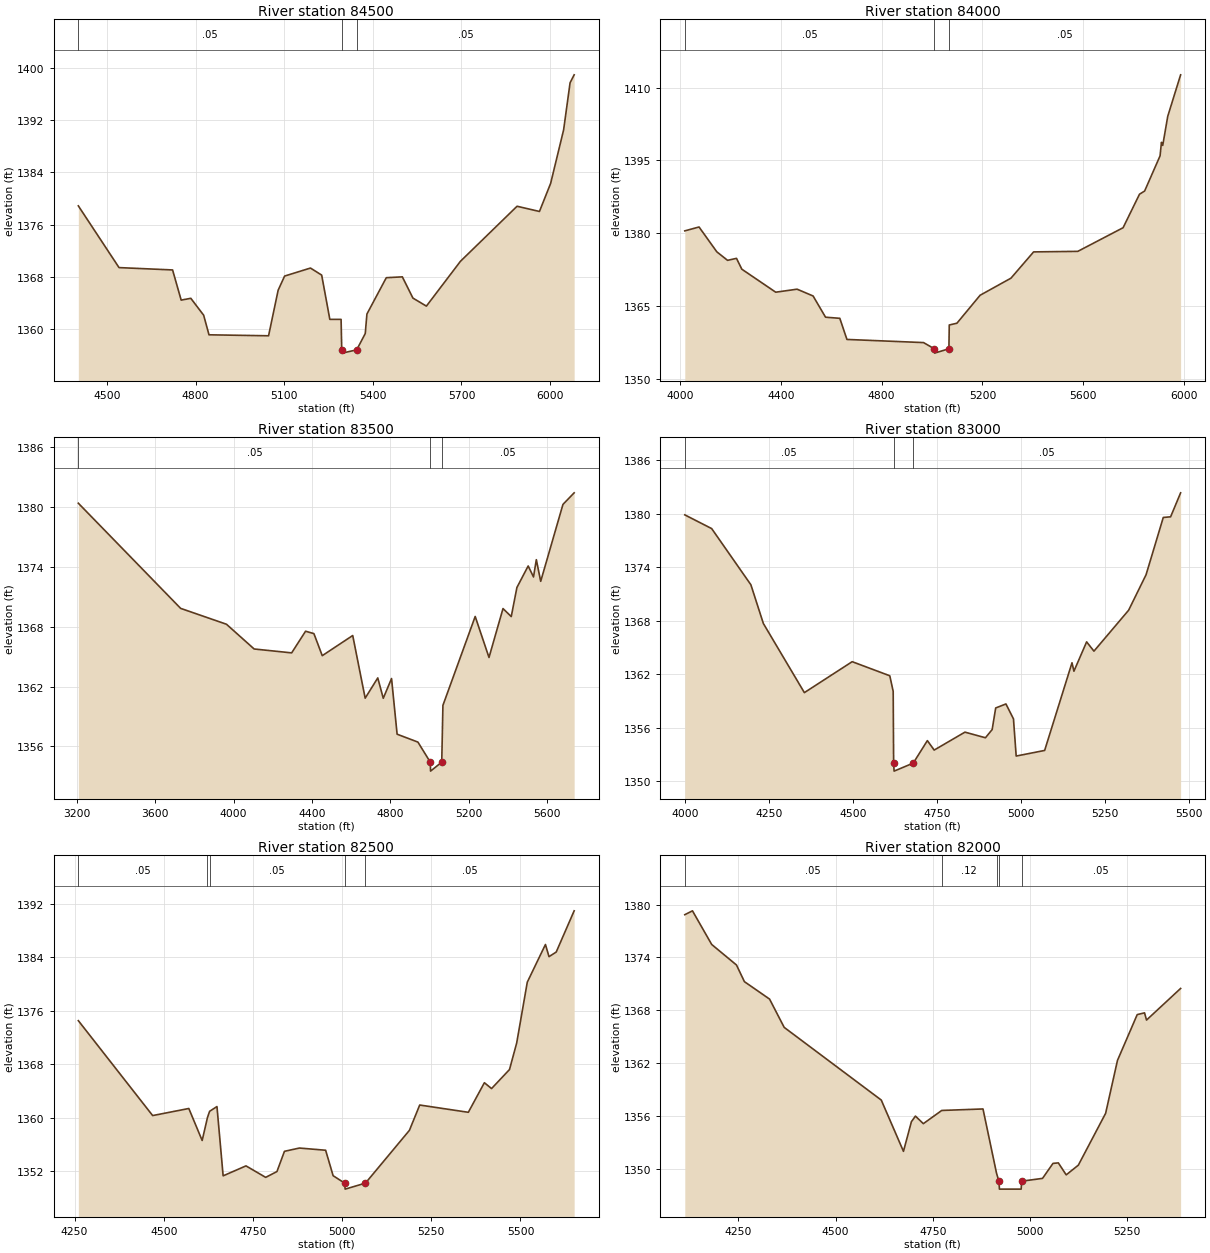
Type RM Length L Ch R = 1 ,84500   ,500,500,500
BEGIN DESCRIPTION:
HICKORY CREEK 169.0
END DESCRIPTION:
XS GIS Cut Line= 3
      2738155.67     10173103.11      2738704.47     10173338.37
      2739655.72     10173853.13
#Sta/Elev= 30
  4402.9 1378.86  4540.7 1369.39    4722 1369.03  4751.1  1364.4  4783.7 1364.68
  4827.2 1362.09  4845.3 1359.08    5047 1358.93  5079.4 1365.92  5101.3 1368.09
  5188.8 1369.32  5226.8 1368.24  5254.4 1361.45  5292.5 1361.45  5294.7 1356.77
  5295.7 1356.27  5345.3 1356.77  5374.3 1359.27    5380 1362.27  5445.6 1367.84
  5499.9 1367.97  5535.8 1364.71  5581.3 1363.48  5696.7 1370.36  5888.3  1378.8
  5964.1    1378    6002 1382.31  6045.9 1390.51  6067.8 1397.74  6081.6 1398.96
#Mann= 3 ,-1 , 0
  4402.9     .05       0  5294.7     .03       0  5345.3     .05       0
Bank Sta=5294.7,5345.3
XS Rating Curve= 0 ,0
Exp/Cntr=0.3,0.1

Type RM Length L Ch R = 1 ,84000   ,500,500,500
BEGIN DESCRIPTION:
HICKORY CREEK 168.0
END DESCRIPTION:
XS GIS Cut Line= 3
      2738055.67      10173103.1      2738738.43     10173807.51
      2739705.65     10174003.11
#Sta/Elev= 30
    4019 1380.49  4075.5 1381.29  4146.2 1376.17  4188.7 1374.42  4224.2 1374.83
  4245.3  1372.6  4379.8 1367.86  4464.7 1368.48  4528.2 1367.08  4577.6 1362.71
  4634.2 1362.48  4662.5 1358.13  4966.6 1357.48  5008.9 1356.21  5010.3 1355.31
  5067.2 1356.21  5068.6  1361.1    5099 1361.47    5191 1367.23  5313.5 1370.75
  5403.4 1376.16  5578.7 1376.27  5758.5 1381.14  5823.6 1388.04    5844  1388.7
  5905.2 1395.94  5910.7 1398.73  5915.8 1398.09  5935.8 1404.11  5986.8 1412.63
#Mann= 3 ,-1 , 0
    4019     .05       0  5008.9     .03       0  5067.2     .05       0
Bank Sta=5008.9,5067.2
XS Rating Curve= 0 ,0
Exp/Cntr=0.3,0.1

Type RM Length L Ch R = 1 ,83500   ,500,500,500
BEGIN DESCRIPTION:
HICKORY CREEK 167.0
END DESCRIPTION:
XS GIS Cut Line= 3
      2737106.27     10172975.54      2738430.71     10174182.66
      2738894.48     10174755.06
#Sta/Elev= 30
    3208 1380.37  3729.8 1369.83  3963.5 1368.24  4104.7 1365.76    4296 1365.37
  4366.9 1367.54  4409.5  1367.3    4452 1365.09  4607.4 1367.11  4670.9 1360.83
  4735.1 1362.86  4763.2 1360.82  4805.4  1362.8  4833.8 1357.22  4939.9 1356.43
    5003 1354.42  5004.4 1353.52  5061.4 1354.42  5067.4 1360.11    5232 1369.02
  5302.4 1364.91  5373.8 1369.81  5415.9 1369.01  5444.7 1371.92  5502.2 1374.08
  5529.4 1372.98  5543.8 1374.71  5566.1 1372.54  5679.6 1380.25  5736.7 1381.41
#Mann= 3 ,-1 , 0
    3208     .05       0    5003     .03       0  5061.4     .05       0
Bank Sta=5003,5061.4
XS Rating Curve= 0 ,0
Exp/Cntr=0.3,0.1

Type RM Length L Ch R = 1 ,83000   ,500,500,500
BEGIN DESCRIPTION:
HICKORY CREEK 166.0
END DESCRIPTION:
XS GIS Cut Line= 3
      2737105.64     10174703.12      2738089.59     10174523.59
      2738505.69     10174753.11
#Sta/Elev= 30
  3999.8 1379.87  4079.8 1378.33  4196.5 1372.03  4233.6 1367.69  4355.6 1359.94
  4497.9 1363.41  4609.8 1361.83  4619.9 1360.08  4621.2 1352.04  4622.6 1351.14
  4679.6 1352.04  4721.6 1354.56  4741.9  1353.5  4833.4 1355.51  4894.4 1354.88
  4914.4  1355.8  4924.9 1358.22  4955.4 1358.67  4977.8    1357  4985.9 1352.83
  5070.6 1353.46    5152 1363.29  5157.7 1362.34  5195.5 1365.63  5217.3 1364.59
  5320.5 1369.18  5372.4 1373.16  5423.6 1379.58  5445.4 1379.65  5475.2 1382.34
#Mann= 3 ,-1 , 0
  3999.8     .05       0  4621.2     .03       0  4679.6     .05       0
Bank Sta=4621.2,4679.6
XS Rating Curve= 0 ,0
Exp/Cntr=0.3,0.1

Type RM Length L Ch R = 1 ,82500   ,500,500,500
BEGIN DESCRIPTION:
HICKORY CREEK 165.0
END DESCRIPTION:
XS GIS Cut Line= 3
      2737255.67     10174753.11      2737959.62     10174979.97
      2738605.67     10174903.11
#Sta/Elev= 30
  4260.4 1374.52  4468.8 1360.31  4570.2 1361.37  4607.6 1356.58  4622.5 1360.02
  4628.5 1360.95  4649.1 1361.66  4666.4 1351.29  4730.5 1352.78  4785.7 1351.06
  4817.3 1351.93  4838.3 1354.96  4880.3 1355.45  4953.8 1355.12  4974.8 1351.31
  5007.1  1350.2  5008.5  1349.3  5065.5  1350.2  5188.7  1358.1  5217.6 1361.89
  5353.9  1360.8  5398.9 1365.23    5419 1364.35  5469.3  1367.2  5489.5 1371.18
  5519.2 1380.28  5570.1 1385.92  5580.1  1384.1  5600.3 1384.79  5650.6 1390.96
#Mann= 5 ,-1 , 0
  4260.4     .05       0  4622.5     .12       0  4628.5     .05       0
  5007.1     .03       0  5065.5     .05       0
Bank Sta=5007.1,5065.5
XS Rating Curve= 0 ,0
Exp/Cntr=0.3,0.1

Type RM Length L Ch R = 1 ,82000   ,500,500,500
BEGIN DESCRIPTION:
HICKORY CREEK 164.0
END DESCRIPTION:
XS GIS Cut Line= 3
      2737155.71     10175653.11      2738024.26     10175468.28
      2738405.73      10175403.1
#Sta/Elev= 30
    4112 1378.85  4131.7 1379.29  4181.2 1375.47  4244.9 1373.14  4265.3 1371.25
    4330 1369.27  4367.6 1366.06  4617.2 1357.81  4674.3 1351.99  4694.7 1355.35
    4705 1355.99  4725.4 1355.13  4772.7 1356.63  4878.8  1356.8  4913.7 1349.49
  4919.7  1348.6  4921.1  1347.7  4976.9  1347.7  4978.3  1348.6  5031.9 1348.92
  5058.8 1350.62  5072.5 1350.68  5092.8 1349.32    5124 1350.42  5194.2 1356.31
  5224.6 1362.31  5275.4 1367.51  5294.2 1367.71  5299.3 1366.89    5387 1370.48
#Mann= 5 ,-1 , 0
    4112     .05       0  4772.7     .12       0  4913.7     .05       0
  4919.7     .03       0  4978.3     .05       0
Bank Sta=4919.7,4978.3
XS Rating Curve= 0 ,0
Exp/Cntr=0.3,0.1