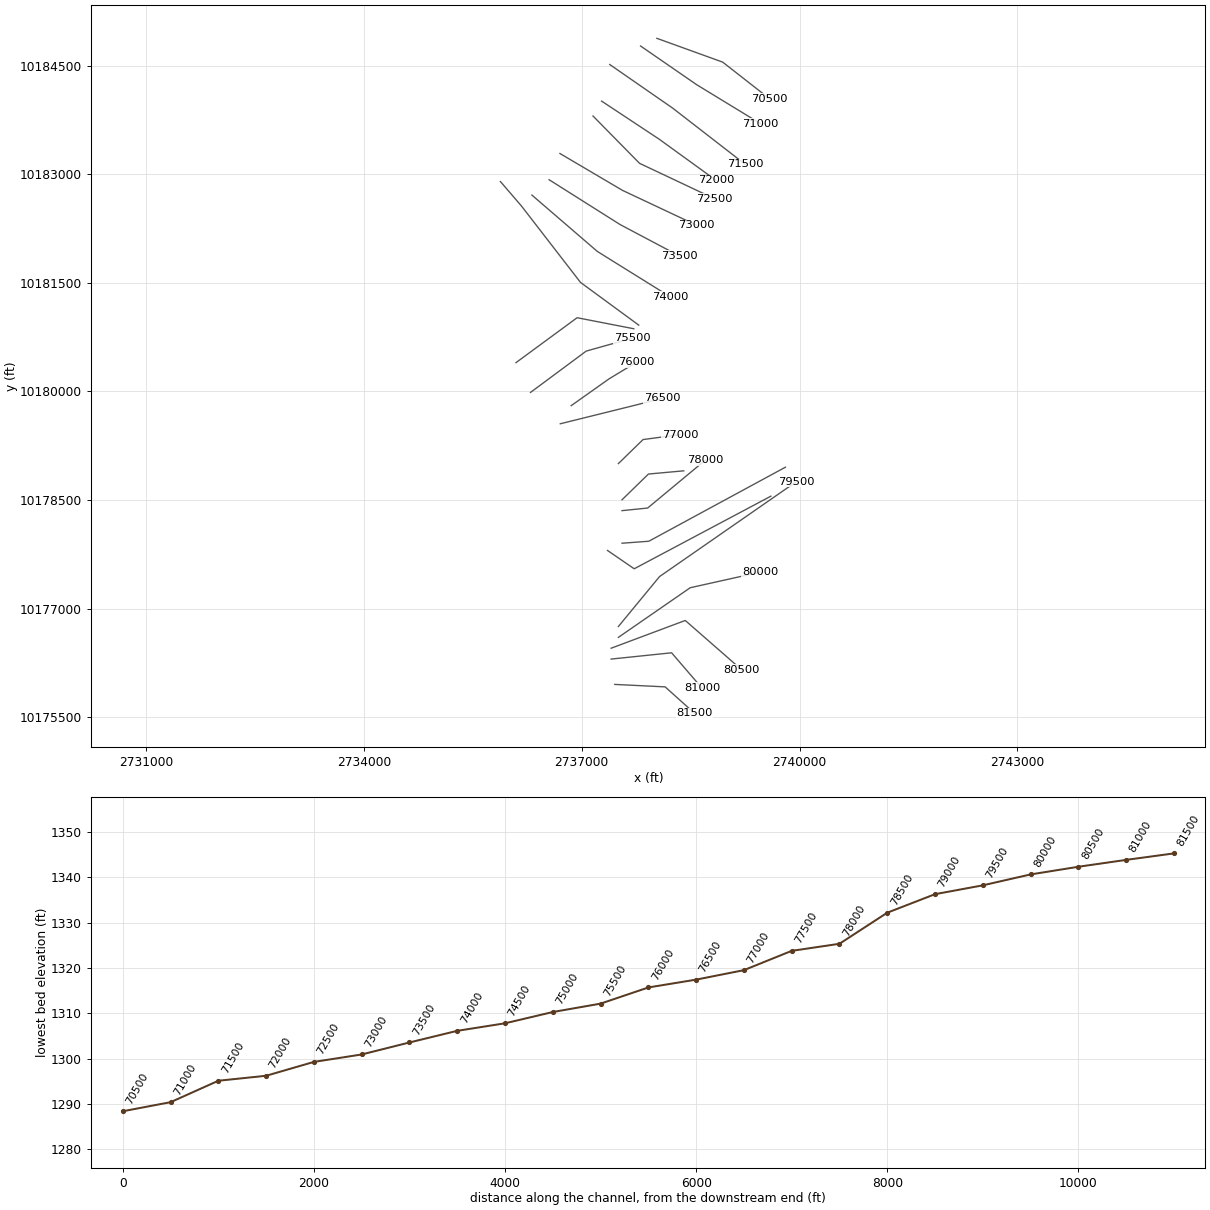
HEC-RAS study HICKORY CREEK.prj: HICKORY CREEK Base Level Engineering

--- HICKORY CREEK.g01 (geometry) --- (continued)

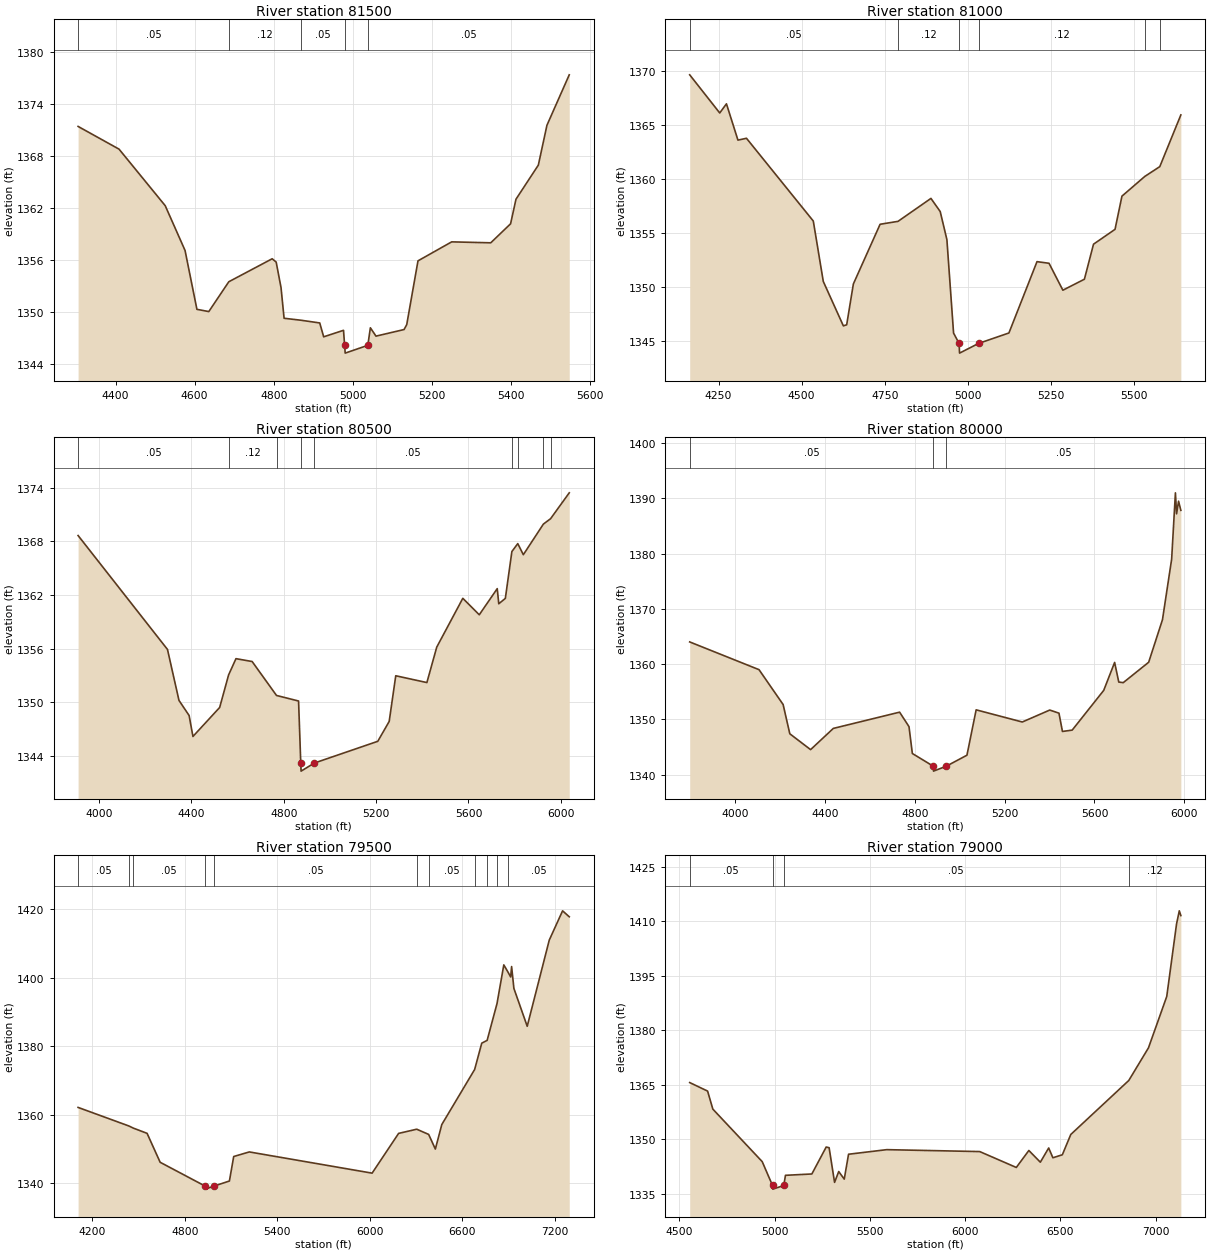
Type RM Length L Ch R = 1 ,81500   ,500,500,500
BEGIN DESCRIPTION:
HICKORY CREEK 163.0
END DESCRIPTION:
XS GIS Cut Line= 3
      2737455.73     10175953.11       2738149.5     10175919.08
      2738555.66     10175553.13
#Sta/Elev= 30
  4305.4 1371.42  4408.9  1368.8  4525.6 1362.28  4575.7 1357.12  4605.7 1350.33
  4635.7 1350.07  4686.3 1353.51  4795.9 1356.16    4806 1355.78  4818.3 1352.83
    4826  1349.3    4869 1349.07  4916.1 1348.76  4926.1 1347.16  4976.2 1347.91
    4979 1346.18  4980.4 1345.28  5037.6 1346.18  5044.1  1348.2  5058.3 1347.24
  5129.3    1348    5136 1348.57  5164.4 1355.92  5249.6 1358.11  5348.3    1358
  5398.4 1360.19  5412.1 1363.03  5468.6 1366.96  5490.3 1371.55  5546.7 1377.37
#Mann= 5 ,-1 , 0
  4305.4     .05       0  4686.3     .12       0    4869     .05       0
    4979     .03       0  5037.6     .05       0
Bank Sta=4979,5037.6
XS Rating Curve= 0 ,0
Exp/Cntr=0.3,0.1

Type RM Length L Ch R = 1 ,81000   ,500,500,500
BEGIN DESCRIPTION:
HICKORY CREEK 162.0
END DESCRIPTION:
XS GIS Cut Line= 3
      2737405.72     10176303.12      2738238.21     10176389.91
      2738655.69     10175903.11
#Sta/Elev= 30
    4163 1369.68  4253.4 1366.14  4273.6 1366.99  4308.2 1363.62  4333.9 1363.79
    4535 1356.11  4565.1  1350.5  4625.5 1346.38  4635.5 1346.48  4655.6 1350.27
  4736.1 1355.81    4790 1356.08  4889.1 1358.21    4917 1356.99  4937.1 1354.39
  4957.2 1345.71  4973.8 1344.75  4975.2 1343.85  5032.4 1344.75  5123.8 1345.72
  5208.3 1352.34  5244.5 1352.19  5286.2 1349.69    5351 1350.71  5378.4 1353.96
  5443.2 1355.34    5464 1358.42  5532.8 1360.25  5577.9 1361.16  5641.3 1365.96
#Mann= 6 ,-1 , 0
    4163     .05       0    4790     .12       0  4973.8     .03       0
  5032.4     .12       0  5532.8     .12       0  5577.9     .05       0
Bank Sta=4973.8,5032.4
XS Rating Curve= 0 ,0
Exp/Cntr=0.3,0.1

Type RM Length L Ch R = 1 ,80500   ,500,500,500
BEGIN DESCRIPTION:
HICKORY CREEK 161.0
END DESCRIPTION:
XS GIS Cut Line= 3
      2737405.67     10176453.11      2738426.33     10176836.25
      2739205.71     10176153.09
#Sta/Elev= 30
  3909.8 1368.64  4296.8 1355.92  4346.6 1350.23  4390.5 1348.54  4407.1  1346.2
  4522.8 1349.44  4561.4 1353.07  4593.4 1354.89  4663.4 1354.57  4768.9 1350.78
  4864.4 1350.16  4873.9 1343.23  4875.3 1342.33  4932.5 1343.23  5207.4 1345.66
  5256.8 1347.88  5285.2 1352.98    5420 1352.22  5462.7 1356.18  5575.6 1361.63
  5646.8 1359.79  5724.6 1362.71  5731.3 1361.02  5759.7 1361.62    5788 1366.85
  5813.5 1367.74  5837.6  1366.5  5924.5 1369.92  5955.6 1370.52  6036.4 1373.41
#Mann= 9 ,-1 , 0
  3909.8     .05       0  4561.4     .12       0  4768.9     .05       0
  4873.9     .05       0  4932.5     .05       0    5788     .12       0
  5813.5     .05       0  5924.5     .12       0  5955.6     .05       0
Bank Sta=4873.9,4932.5
XS Rating Curve= 0 ,0
Exp/Cntr=0.3,0.1

Type RM Length L Ch R = 1 ,80000   ,500,500,500
BEGIN DESCRIPTION:
HICKORY CREEK 160.0
END DESCRIPTION:
XS GIS Cut Line= 3
      2737505.67      10176603.1      2738494.65     10177288.38
      2739455.65      10177503.1
#Sta/Elev= 30
  3796.8 1364.02  4105.6    1359    4213 1352.69  4242.7  1347.4  4335.3 1344.53
  4436.6 1348.37  4731.8 1351.31  4773.7 1348.69  4788.6 1343.83  4881.5 1341.54
    4883 1340.64  4940.2 1341.54  5031.8 1343.52  5072.8 1351.73  5278.4 1349.53
  5400.7 1351.69  5441.7 1351.13  5457.2 1347.82  5500.6 1348.06  5641.1 1355.25
  5689.7 1360.31  5708.1 1356.76    5728 1356.65  5841.3 1360.34  5902.8 1368.04
  5943.7    1379  5960.5    1391  5965.6  1387.2  5974.5 1389.49  5984.7 1387.83
#Mann= 3 ,-1 , 0
  3796.8     .05       0  4881.5     .03       0  4940.2     .05       0
Bank Sta=4881.5,4940.2
XS Rating Curve= 0 ,0
Exp/Cntr=0.3,0.1

Type RM Length L Ch R = 1 ,79500   ,500,500,500
BEGIN DESCRIPTION:
HICKORY CREEK 159.0
END DESCRIPTION:
XS GIS Cut Line= 3
      2737505.68      10176753.1      2738072.14      10177442.4
      2739955.68     10178753.11
#Sta/Elev= 30
  4107.8 1362.11    4436 1356.71  4465.9 1356.07  4555.5 1354.53  4640.2 1346.08
  4931.6 1339.13    4933 1338.23  4990.3 1339.13  5089.6  1340.6  5117.5 1347.76
  5218.8  1349.1  6015.5  1342.9  6187.6 1354.52  6305.1 1355.74  6382.5 1354.22
  6425.9 1349.94  6467.7  1357.1  6680.9  1373.2    6727  1380.9  6761.9  1381.7
    6826 1392.46  6870.1 1403.77  6894.7 1401.86  6914.6 1400.25  6920.7 1403.28
  6935.6 1396.88    7022 1385.83  7165.1 1411.02  7251.5 1419.57  7294.7 1417.83
#Mann= 11 ,-1 , 0
  4107.8     .05       0    4436     .12       0  4465.9     .05       0
  4931.6     .03       0  4990.3     .05       0  6305.1     .12       0
  6382.5     .05       0  6680.9     .12       0  6761.9     .05       0
    6826     .12       0  6894.7     .05       0
Bank Sta=4931.6,4990.3
XS Rating Curve= 0 ,0
Exp/Cntr=0.3,0.1

Type RM Length L Ch R = 1 ,79000   ,500,500,500
BEGIN DESCRIPTION:
HICKORY CREEK 158.0
END DESCRIPTION:
XS GIS Cut Line= 3
       2737355.7      10177803.1      2737723.42     10177550.18
      2739605.69     10178553.12
#Sta/Elev= 30
  4553.7  1365.6  4647.7 1363.25  4675.1  1358.3  4934.5 1343.84  4988.6 1337.28
  4990.1 1336.28  5047.8 1337.28  5056.5 1340.08  5195.2 1340.45  5270.4 1347.86
  5285.8 1347.67  5314.4 1338.14  5336.3 1341.12  5365.2 1339.03  5387.8 1345.88
  5588.6 1347.14  6076.7 1346.61  6268.7 1342.24  6334.6 1346.91  6394.9 1343.69
  6438.8  1347.6  6460.8 1344.91  6510.4 1345.73  6554.9 1351.32  6859.5 1366.18
  6962.8 1375.16  7058.7 1389.28  7110.1 1409.22  7124.6 1412.85  7132.8 1411.54
#Mann= 4 ,-1 , 0
  4553.7     .05       0  4988.6     .03       0  5047.8     .05       0
  6859.5     .12       0
Bank Sta=4988.6,5047.8
XS Rating Curve= 0 ,0
Exp/Cntr=0.3,0.1

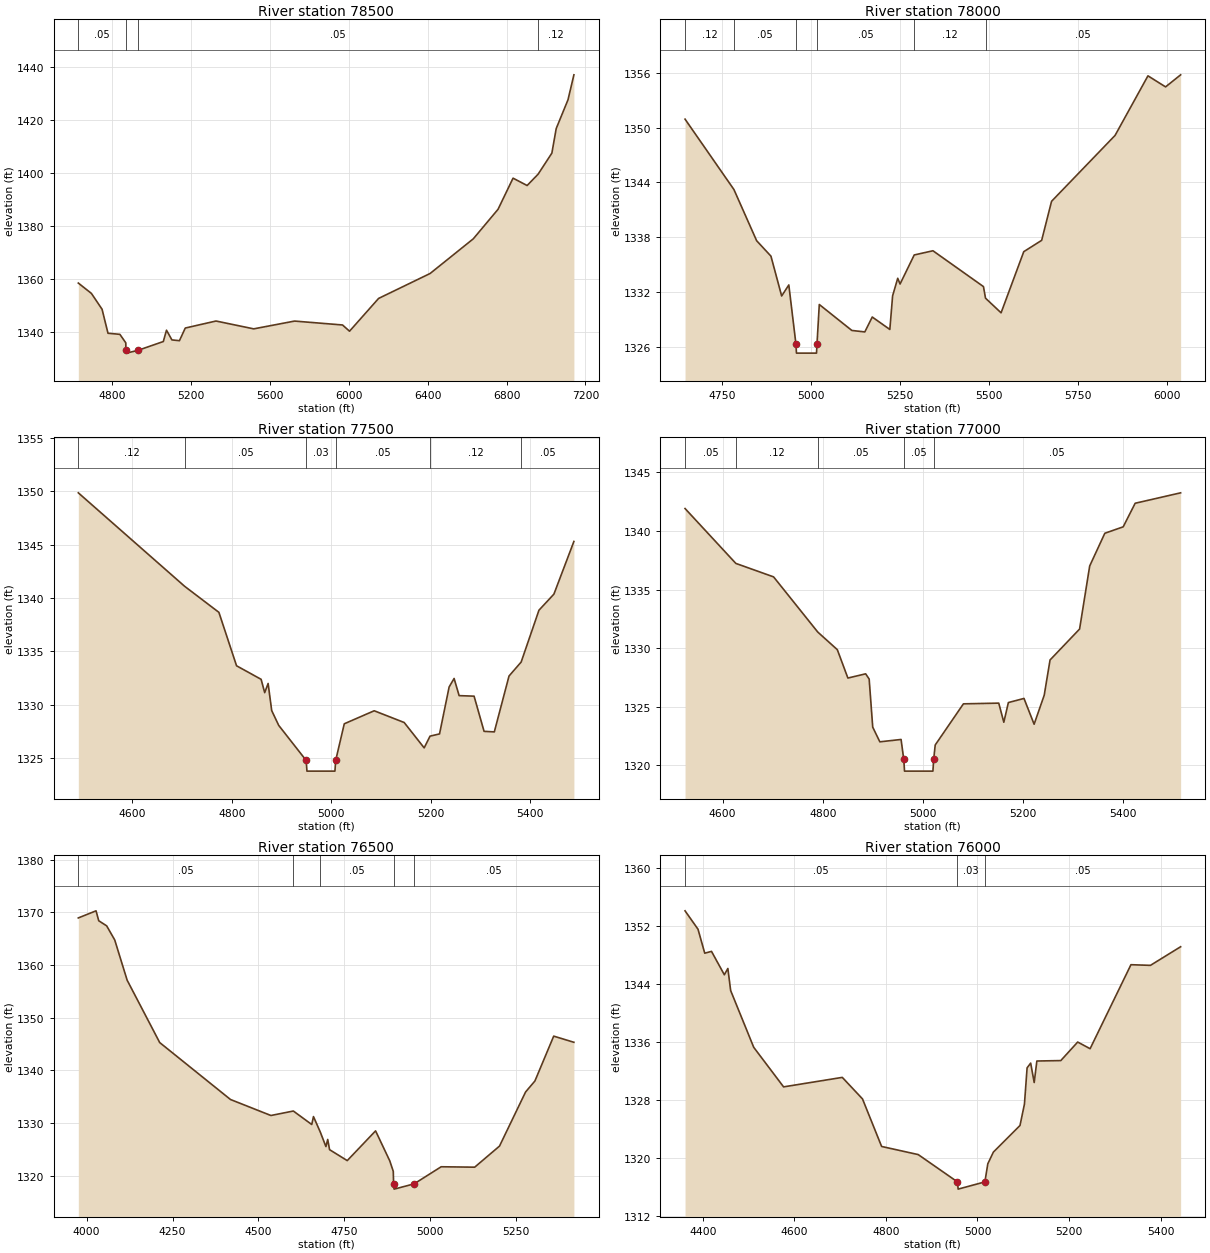
Type RM Length L Ch R = 1 ,78500   ,500,500,500
BEGIN DESCRIPTION:
HICKORY CREEK 157.0
END DESCRIPTION:
XS GIS Cut Line= 3
      2737555.71     10177903.11       2737924.3     10177930.49
      2739805.64     10178953.09
#Sta/Elev= 30
  4630.4 1358.55  4696.7 1354.66  4750.7  1348.7  4780.8 1339.66    4841 1339.26
    4871 1336.06  4871.5 1333.19    4873 1332.19  4930.7 1333.19    5061 1336.55
  5077.2 1340.81  5104.7 1337.16  5142.7 1336.87  5172.3 1341.63    5328 1344.27
    5519 1341.32  5726.1 1344.25    5969 1342.78  6004.5 1340.44  6151.8 1352.77
  6412.9 1362.16  6631.6  1375.2    6757 1386.31    6833 1398.02  6904.3 1395.25
  6960.2 1399.54  7029.7 1407.45  7051.6 1416.68  7111.4 1427.51  7141.3  1436.9
#Mann= 4 ,-1 , 0
  4630.4     .05       0  4871.5     .03       0  4930.7     .05       0
  6960.2     .12       0
Bank Sta=4871.5,4930.7
XS Rating Curve= 0 ,0
Exp/Cntr=0.3,0.1

Type RM Length L Ch R = 1 ,78000   ,500,500,500
BEGIN DESCRIPTION:
HICKORY CREEK 156.0
END DESCRIPTION:
XS GIS Cut Line= 3
      2737555.64     10178353.11      2737908.32     10178389.02
      2738705.69     10179053.12
#Sta/Elev= 30
  4645.5 1350.93  4782.8 1343.23  4846.6 1337.63  4886.8 1335.94  4916.9 1331.58
    4937 1332.79    4957 1326.33  4958.5 1325.33  5014.8 1325.33  5016.2 1326.33
  5022.6 1330.65  5114.1 1327.81  5150.5 1327.65  5171.4 1329.28  5220.8 1327.92
  5228.6  1331.6    5243 1333.52  5249.5 1332.89  5289.3 1336.07  5341.9 1336.53
  5483.8 1332.61  5489.6 1331.34  5533.3 1329.74    5597 1336.43  5647.3 1337.67
  5675.1 1341.94  5853.5 1349.15  5945.9 1355.67  5995.4 1354.46  6037.7 1355.78
#Mann= 6 ,-1 , 0
  4645.5     .12       0  4782.8     .05       0    4957     .03       0
  5016.2     .05       0  5289.3     .12       0  5489.6     .05       0
Bank Sta=4957,5016.2
XS Rating Curve= 0 ,0
Exp/Cntr=0.3,0.1

Type RM Length L Ch R = 1 ,77500   ,500,500,500
BEGIN DESCRIPTION:
HICKORY CREEK 155.0
END DESCRIPTION:
XS GIS Cut Line= 3
      2737555.67      10178503.1       2737919.5     10178858.64
      2738405.67     10178903.11
#Sta/Elev= 30
  4491.3 1349.87    4705 1341.11  4774.1 1338.66  4809.6 1333.65    4859 1332.38
  4866.2 1331.13  4873.1 1331.99  4880.3 1329.45  4894.4 1328.06  4949.7 1324.77
  4951.2 1323.77  5007.5 1323.77    5009 1324.77  5026.3 1328.21  5086.5 1329.43
  5146.8 1328.33    5187 1325.95  5198.8 1327.05  5217.9 1327.26  5237.2 1331.66
  5247.2 1332.46  5257.3 1330.85  5287.4  1330.8  5307.5  1327.5  5328.1 1327.45
  5357.7 1332.69  5382.1    1334  5417.9 1338.86    5448 1340.37  5488.2 1345.31
#Mann= 6 ,-1 , 0
  4491.3     .12       0    4705     .05       0  4949.7     .03       0
    5009     .05       0  5198.8     .12       0  5382.1     .05       0
Bank Sta=4949.7,5009
XS Rating Curve= 0 ,0
Exp/Cntr=0.3,0.1

Type RM Length L Ch R = 1 ,77000   ,500,500,500
BEGIN DESCRIPTION:
HICKORY CREEK 154.0
END DESCRIPTION:
XS GIS Cut Line= 3
       2737505.7     10179003.13      2737845.44     10179334.95
      2738355.71     10179403.12
#Sta/Elev= 30
  4525.1 1341.91  4626.5 1337.23  4701.9 1336.08  4790.2 1331.37  4829.2 1329.87
  4850.3 1327.45  4885.8 1327.81  4892.8 1327.36  4899.9 1323.26  4914.1 1322.01
  4956.5 1322.21  4961.9 1320.51  4963.4 1319.51  5020.1 1319.51  5021.6 1320.51
  5024.7 1321.74    5081 1325.25  5151.6 1325.31  5161.7 1323.68  5170.8 1325.36
    5202 1325.71  5222.2 1323.51  5242.4 1325.99    5254 1328.99    5313 1331.63
  5333.2 1337.01  5363.4  1339.8  5400.1 1340.35    5424 1342.36  5514.8 1343.25
#Mann= 5 ,-1 , 0
  4525.1     .05       0  4626.5     .12       0  4790.2     .05       0
  4961.9     .05       0  5021.6     .05       0
Bank Sta=4961.9,5021.6
XS Rating Curve= 0 ,0
Exp/Cntr=0.3,0.1

Type RM Length L Ch R = 1 ,76500   ,500,500,500
BEGIN DESCRIPTION:
HICKORY CREEK 153.0
END DESCRIPTION:
XS GIS Cut Line= 3
      2736705.65      10179553.1      2737699.74     10179800.06
      2738105.66     10179903.11
#Sta/Elev= 30
  3975.7 1368.95  4027.3  1370.3  4035.2 1368.41  4058.2 1367.45  4081.7 1364.77
  4117.9 1357.12  4212.7 1345.27  4418.8 1334.45  4536.5 1331.41  4601.8 1332.26
  4655.4  1329.7  4660.5  1331.2  4680.2 1328.28  4696.7  1325.5  4701.9 1326.86
  4707.3 1324.92  4758.8 1322.84  4841.3 1328.49  4882.5 1322.81  4892.8 1320.81
  4893.8 1318.42  4895.3 1317.42  4953.5 1318.42  5032.3 1321.67  5129.9 1321.59
  5202.2  1325.6  5278.1 1335.88  5305.3 1337.97    5360 1346.49  5418.8 1345.32
#Mann= 5 ,-1 , 0
  3975.7     .05       0  4601.8     .12       0  4680.2     .05       0
  4893.8     .03       0  4953.5     .05       0
Bank Sta=4893.8,4953.5
XS Rating Curve= 0 ,0
Exp/Cntr=0.3,0.1

Type RM Length L Ch R = 1 ,76000   ,500,500,500
BEGIN DESCRIPTION:
HICKORY CREEK 152.0
END DESCRIPTION:
XS GIS Cut Line= 3
       2736855.7     10179803.12      2737376.39     10180172.84
      2737755.66      10180403.1
#Sta/Elev= 30
  4361.4 1354.12  4389.7 1351.58  4404.4 1348.27  4419.2 1348.52  4447.2 1345.29
  4454.9 1346.16    4461 1343.11  4511.4 1335.27  4576.6 1329.81  4704.8 1331.12
  4748.9 1328.15  4790.7 1321.58  4870.6 1320.46  4956.3 1316.69  4957.8 1315.69
  5016.2 1316.69  5022.6 1319.19  5034.8 1320.81  5092.9 1324.48  5102.6 1327.43
  5108.4 1332.44  5116.2 1333.09  5123.9 1330.41  5129.7 1333.38    5182 1333.44
  5218.9    1336    5246 1335.08  5335.2 1346.68  5377.8 1346.59  5443.7 1349.16
#Mann= 3 ,-1 , 0
  4361.4     .05       0  4956.3     .03       0  5016.2     .05       0
Bank Sta=4956.3,5016.2
XS Rating Curve= 0 ,0
Exp/Cntr=0.3,0.1

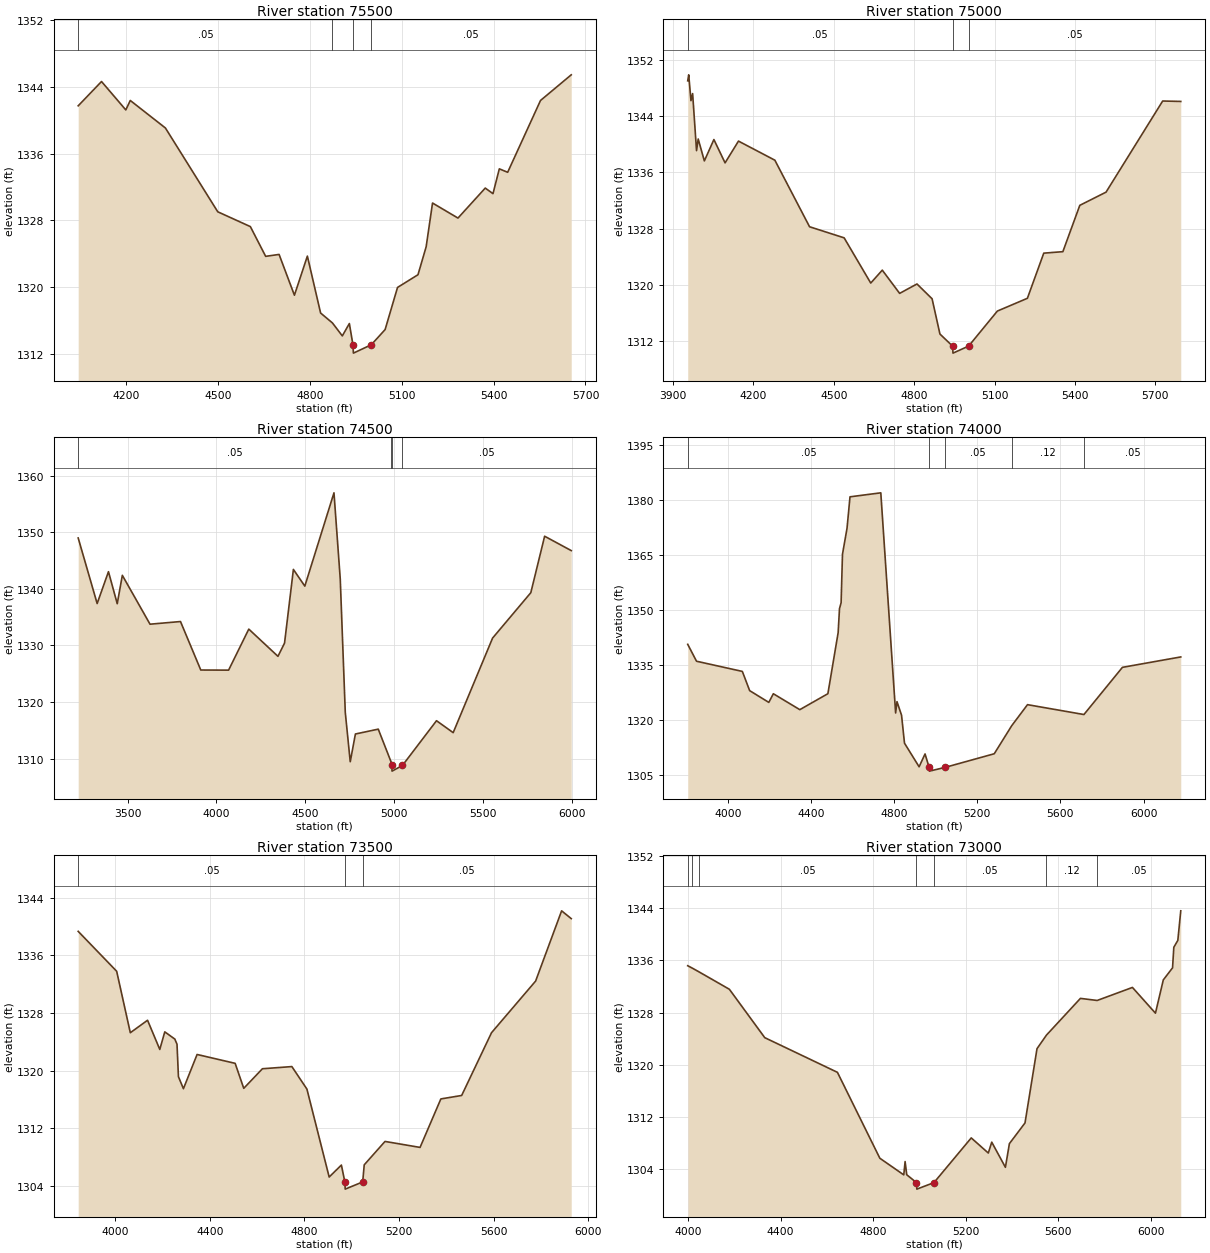
Type RM Length L Ch R = 1 ,75500   ,500,500,500
BEGIN DESCRIPTION:
HICKORY CREEK 151.0
END DESCRIPTION:
XS GIS Cut Line= 3
       2736295.3     10179985.76      2737062.65     10180556.78
      2737691.65     10180734.05
#Sta/Elev= 30
  4043.5 1341.71  4119.7 1344.62    4199 1341.22  4213.6 1342.35  4328.3 1339.06
  4499.3 1329.03  4605.7 1327.26  4655.7  1323.7  4699.5 1323.93  4749.6 1319.05
  4791.9 1323.73  4835.1 1316.92  4873.8 1315.73    4906 1314.18    4929 1315.66
  4940.7 1313.12  4942.2 1312.12  5000.6 1313.12  5045.8 1314.94  5086.3 1319.98
  5153.1  1321.5  5179.8 1324.85  5200.6 1330.08  5283.7 1328.28  5372.8 1331.87
    5398  1331.2  5418.7 1334.17    5446 1333.76  5553.2 1342.35  5653.5 1345.42
#Mann= 4 ,-1 , 0
  4043.5     .05       0  4873.8     .12       0  4940.7     .03       0
  5000.6     .05       0
Bank Sta=4940.7,5000.6
XS Rating Curve= 0 ,0
Exp/Cntr=0.3,0.1

Type RM Length L Ch R = 1 ,75000   ,500,500,500
BEGIN DESCRIPTION:
HICKORY CREEK 150.0
END DESCRIPTION:
XS GIS Cut Line= 3
      2736095.68     10180397.46      2736937.23     10181017.66
       2737717.6      10180865.3
#Sta/Elev= 30
  3954.6 1349.06  3958.3 1349.91  3966.7 1346.23  3972.9 1347.24  3987.5 1339.11
  3993.7 1340.77  4016.7 1337.65  4052.3 1340.69    4094 1337.37  4144.1 1340.47
  4279.9 1337.75  4409.4 1328.27  4538.5 1326.69  4637.8 1320.25  4680.9 1322.09
  4745.7 1318.78  4810.4 1320.12  4866.8 1318.01  4896.1 1312.99  4943.3 1311.27
  4944.8 1310.27  5003.2 1311.27  5110.5 1316.26  5222.6 1318.08  5283.7 1324.51
    5355 1324.72  5418.2 1331.32  5516.2  1333.2  5727.6 1346.18  5795.1 1346.12
#Mann= 3 ,-1 , 0
  3954.6     .05       0  4943.3     .05       0  5003.2     .05       0
Bank Sta=4943.3,5003.2
XS Rating Curve= 0 ,0
Exp/Cntr=0.3,0.1

Type RM Length L Ch R = 1 ,74500   ,500,500,500
BEGIN DESCRIPTION:
HICKORY CREEK 149.0
END DESCRIPTION:
XS GIS Cut Line= 4
       2735880.7      10182898.5      2736170.66     10182560.68
      2736983.99     10181505.07      2737786.17     10180915.21
#Sta/Elev= 30
  3222.2 1348.99  3328.9  1337.4  3392.5 1343.03  3441.9 1337.37  3470.5 1342.39
  3626.3 1333.75  3797.7 1334.22  3911.8 1325.65  4068.3 1325.63  4181.9 1332.88
    4346 1328.07    4383 1330.41  4432.8 1343.43  4497.1 1340.48  4661.1 1356.97
  4696.4 1341.73  4724.7 1318.15  4752.6 1309.44  4781.6 1314.34  4910.2  1315.2
  4983.6 1309.31  4986.2 1308.78  4987.7 1307.78  5046.2 1308.78  5237.9 1316.69
  5331.7 1314.58  5553.2 1331.29  5768.4 1339.32  5846.1  1349.3  5995.7 1346.76
#Mann= 4 ,-1 , 0
  3222.2     .05       0  4983.6     .12       0  4986.2     .07       0
  5046.2     .05       0
Bank Sta=4986.2,5046.2
XS Rating Curve= 0 ,0
Exp/Cntr=0.3,0.1

Type RM Length L Ch R = 1 ,74000   ,500,500,500
BEGIN DESCRIPTION:
HICKORY CREEK 148.0
END DESCRIPTION:
XS GIS Cut Line= 3
      2736314.04     10182711.71      2737216.35     10181932.49
      2738216.61     10181308.19
#Sta/Elev= 30
  3807.8 1340.71  3850.1  1336.1  4070.5 1333.32  4105.6 1328.08  4197.8 1324.87
  4219.6 1327.23  4346.9 1322.89  4481.9 1327.24  4531.2 1343.87  4537.8 1350.46
  4545.5 1352.05  4552.1 1365.27    4574 1372.39  4588.3 1380.95  4736.4 1382.04
  4807.7 1321.99  4814.3 1325.07  4836.2 1321.37  4850.4 1313.74  4920.7  1307.3
  4949.2 1310.81  4968.9 1307.12  4970.4 1306.12  5044.4 1307.12  5282.1 1310.86
  5366.2 1318.52    5442 1324.25  5713.4 1321.56  5898.5 1334.43  6179.1 1337.27
#Mann= 5 ,-1 , 0
  3807.8     .05       0  4968.9     .03       0  5044.4     .05       0
  5366.2     .12       0  5713.4     .05       0
Bank Sta=4968.9,5044.4
XS Rating Curve= 0 ,0
Exp/Cntr=0.3,0.1

Type RM Length L Ch R = 1 ,73500   ,500,500,500
BEGIN DESCRIPTION:
HICKORY CREEK 147.0
END DESCRIPTION:
XS GIS Cut Line= 3
      2736551.05     10182923.83      2737528.02     10182304.95
      2738347.57     10181869.62
#Sta/Elev= 30
  3843.5 1339.33  4006.2 1333.79  4063.9 1325.26  4136.8 1326.99  4188.5 1322.94
  4209.6 1325.38    4252 1324.38  4261.3 1323.66  4267.3 1319.16  4288.4 1317.49
  4346.2 1322.24  4507.1 1321.01  4543.5 1317.54  4622.4 1320.26  4746.9 1320.56
  4810.5 1317.44  4904.6 1305.23  4956.3 1306.89  4970.9 1304.55  4972.4 1303.55
  5046.4 1304.55  5052.8 1306.92  5140.7 1310.17  5288.9 1309.34  5376.8 1316.07
  5464.8 1316.55    5591 1325.26  5777.5 1332.43  5887.4 1342.18    5928  1341.1
#Mann= 3 ,-1 , 0
  3843.5     .05       0  4970.9     .03       0  5046.4     .05       0
Bank Sta=4970.9,5046.4
XS Rating Curve= 0 ,0
Exp/Cntr=0.3,0.1

Type RM Length L Ch R = 1 ,73000   ,500,500,500
BEGIN DESCRIPTION:
HICKORY CREEK 146.0
END DESCRIPTION:
XS GIS Cut Line= 3
      2736700.73     10183285.65      2737562.79     10182776.08
      2738584.59     10182293.81
#Sta/Elev= 30
  3998.6 1335.19  4017.5 1334.84  4045.8 1334.28  4178.6 1331.58  4331.6 1324.15
  4645.7 1318.83  4829.1 1305.64  4932.5 1303.09  4938.3 1305.13  4945.3 1303.11
  4987.5  1301.9    4989  1300.9  5063.1  1301.9  5224.2 1308.76    5298 1306.44
  5312.8 1308.11  5371.9 1304.25  5389.1 1307.88  5456.6 1311.06  5508.5 1322.46
  5549.3 1324.54  5696.2 1330.18  5768.6 1329.86    5921 1331.86  6020.5 1327.91
  6054.4 1333.01  6094.4 1334.87  6099.9 1338.03  6117.2 1339.08  6129.9 1343.62
#Mann= 7 ,-1 , 0
  3998.6     .05       0  4017.5     .12       0  4045.8     .05       0
  4987.5     .03       0  5063.1     .05       0  5549.3     .12       0
  5768.6     .05       0
Bank Sta=4987.5,5063.1
XS Rating Curve= 0 ,0
Exp/Cntr=0.3,0.1

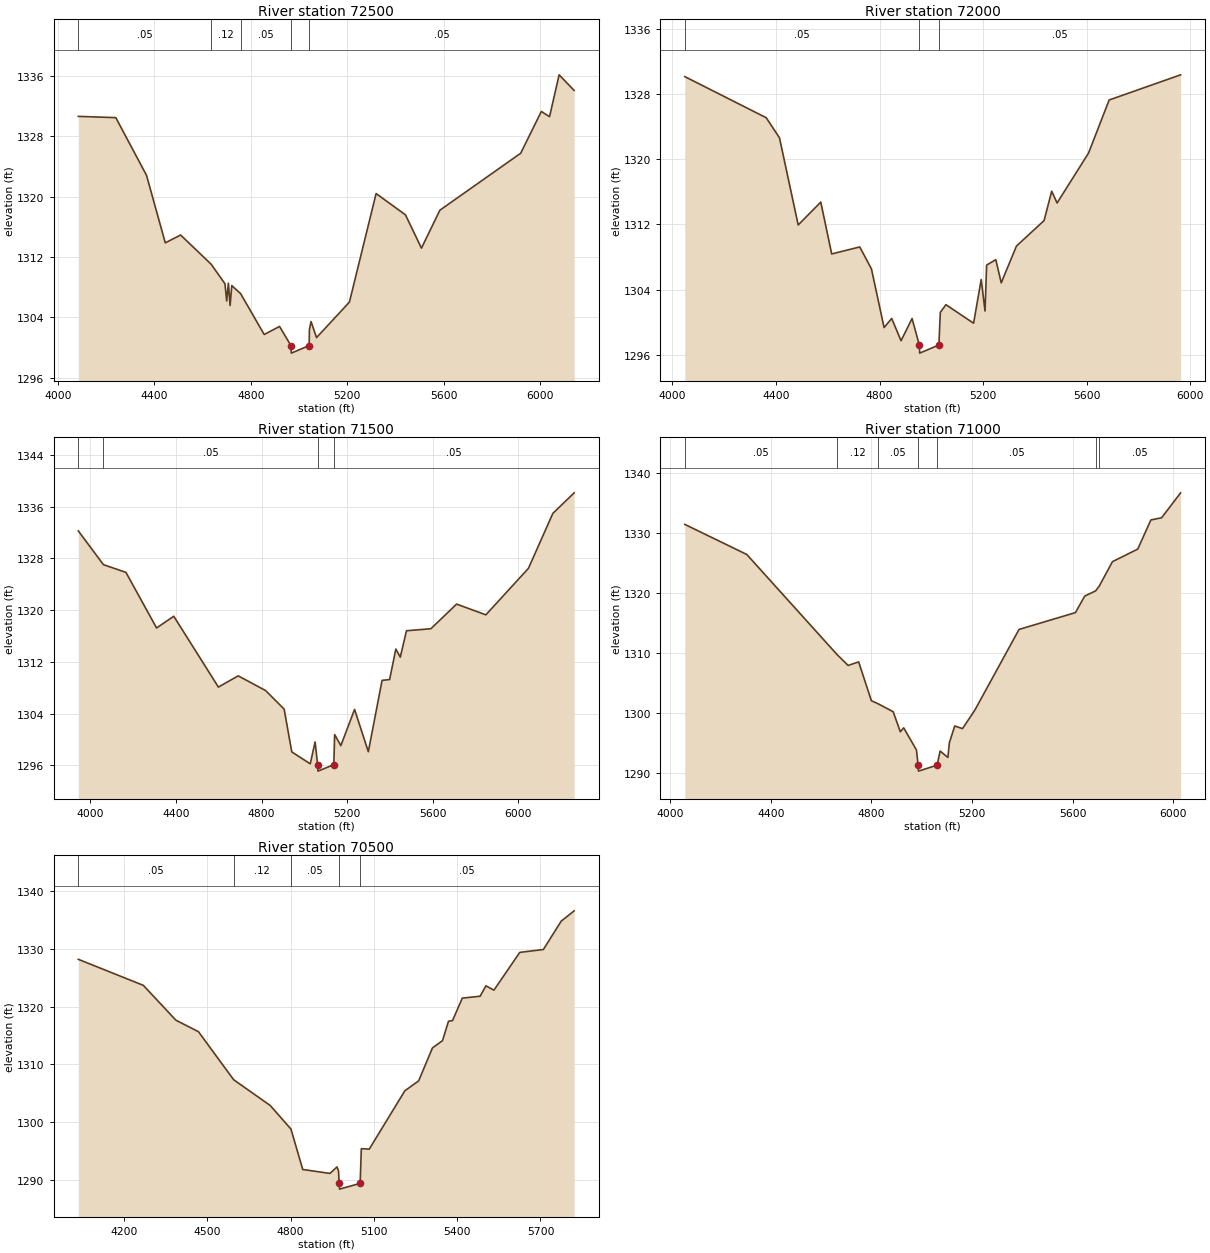
Type RM Length L Ch R = 1 ,72500   ,500,500,500
BEGIN DESCRIPTION:
HICKORY CREEK 145.0
END DESCRIPTION:
XS GIS Cut Line= 3
      2737156.12     10183803.39      2737796.98     10183149.89
      2738827.89     10182661.84
#Sta/Elev= 30
  4084.7 1330.67  4240.1  1330.5  4367.4 1322.85  4445.3 1313.89  4508.8 1314.93
  4635.6 1311.05  4692.7 1308.46  4699.9 1306.18  4706.9 1308.54    4714 1305.58
    4721 1308.22  4757.7 1307.15  4855.4 1301.73    4919  1302.8  4966.3 1300.26
  4967.8 1299.26  5041.9 1300.26  5042.8 1302.35  5049.6 1303.45  5072.4 1301.32
  5208.8 1306.03  5319.4 1320.43  5441.1 1317.61  5507.5 1313.19  5583.9 1318.22
    5919 1325.78  6004.5 1331.32  6038.6 1330.63  6078.2 1336.18  6140.6 1334.11
#Mann= 5 ,-1 , 0
  4084.7     .05       0  4635.6     .12       0  4757.7     .05       0
  4966.3     .05       0  5041.9     .05       0
Bank Sta=4966.3,5041.9
XS Rating Curve= 0 ,0
Exp/Cntr=0.3,0.1

Type RM Length L Ch R = 1 ,72000   ,500,500,500
BEGIN DESCRIPTION:
HICKORY CREEK 144.0
END DESCRIPTION:
XS GIS Cut Line= 3
      2737274.67     10184009.21      2738067.76     10183483.15
      2738846.26     10182917.84
#Sta/Elev= 30
  4048.3 1330.16  4362.7 1325.11  4413.8 1322.64    4486 1311.94  4573.2 1314.75
  4615.3 1308.38  4723.6 1309.24  4768.7 1306.55  4817.5 1299.34  4846.9 1300.46
    4883 1297.72  4925.5 1300.45  4953.5  1297.2    4955  1296.2  5029.1  1297.2
  5034.5 1301.21  5056.3 1302.15    5163 1299.87  5192.4 1305.24  5207.1 1301.37
  5213.3 1307.01  5248.8 1307.68  5269.7 1304.83  5328.4 1309.35  5435.1 1312.48
  5464.5 1316.09  5485.3 1314.64  5606.7 1320.77  5686.3 1327.29  5962.1 1330.38
#Mann= 3 ,-1 , 0
  4048.3     .05       0  4953.5     .03       0  5029.1     .05       0
Bank Sta=4953.5,5029.1
XS Rating Curve= 0 ,0
Exp/Cntr=0.3,0.1

Type RM Length L Ch R = 1 ,71500   ,500,500,500
BEGIN DESCRIPTION:
HICKORY CREEK 143.0
END DESCRIPTION:
XS GIS Cut Line= 3
      2737386.93      10184514.5      2738254.13     10183911.57
        2739250.     10183137.53
#Sta/Elev= 30
  3943.8 1332.23    4061 1327.02  4166.4 1325.82  4309.5 1317.23  4389.9 1319.04
  4598.5 1308.09    4691 1309.83  4819.3 1307.55  4905.7 1304.69  4941.5 1298.07
  5027.8 1296.23  5050.4 1299.61  5062.4  1296.1  5063.9  1295.1    5138  1296.1
  5141.8 1300.75  5170.8 1299.04    5235 1304.64  5299.3  1298.1  5363.5 1309.13
  5398.8 1309.26  5427.8 1313.97  5448.6 1312.72  5477.6  1316.8  5591.6 1317.11
  5711.9 1320.92  5848.6 1319.26  6047.7 1326.45  6161.7 1334.94  6261.3 1338.12
#Mann= 4 ,-1 , 0
  3943.8     .12       0    4061     .05       0  5062.4     .05       0
    5138     .05       0
Bank Sta=5062.4,5138
XS Rating Curve= 0 ,0
Exp/Cntr=0.3,0.1

Type RM Length L Ch R = 1 ,71000   ,500,500,500
BEGIN DESCRIPTION:
HICKORY CREEK 142.0
END DESCRIPTION:
XS GIS Cut Line= 3
       2737811.1     10184770.27      2738585.62     10184234.63
      2739463.55      10183697.7
#Sta/Elev= 30
  4058.3 1331.41  4304.6 1326.41  4663.3 1309.77  4707.4 1307.95  4749.3 1308.54
    4800 1302.08  4825.9 1301.59  4886.5 1300.25    4915 1296.92  4928.4 1297.57
  4979.1 1293.89  4985.7 1291.37  4987.2 1290.37  5061.4 1291.37  5073.1 1293.71
    5104 1292.65  5109.9 1295.08  5131.2 1297.88  5162.1 1297.44  5211.1 1300.51
  5386.9 1313.94  5611.1 1316.74  5647.8 1319.48  5691.2 1320.35  5705.2 1321.11
  5758.1 1325.21  5858.7  1327.3  5910.9 1332.15  5953.5 1332.51  6029.1 1336.66
#Mann= 7 ,-1 , 0
  4058.3     .05       0  4663.3     .12       0  4825.9     .05       0
  4985.7     .05       0  5061.4     .05       0  5691.2     .12       0
  5705.2     .05       0
Bank Sta=4985.7,5061.4
XS Rating Curve= 0 ,0
Exp/Cntr=0.3,0.1

Type RM Length L Ch R = 1 ,70500   ,500,500,500
BEGIN DESCRIPTION:
HICKORY CREEK 141.0
END DESCRIPTION:
XS GIS Cut Line= 3
      2738035.71     10184876.28      2738942.69     10184547.31
      2739588.91     10184040.42
#Sta/Elev= 30
  4035.2 1328.17  4269.5 1323.66  4386.6 1317.63  4467.9 1315.64  4594.7 1307.32
  4726.6 1302.85  4801.2 1298.77  4843.6 1291.77  4941.8 1291.09  4967.1 1292.22
  4972.5 1291.49  4974.7 1289.37  4976.2 1288.37  5050.4 1289.37  5054.6 1295.38
  5083.1 1295.29  5211.4  1305.4  5261.1 1307.12  5310.9 1312.83    5347 1314.08
  5368.7 1317.45  5383.1 1317.55  5418.4 1321.45  5482.6 1321.78  5503.4 1323.58
  5532.3 1322.83  5625.4 1329.37  5710.4 1329.87  5774.6 1334.78  5821.3 1336.57
#Mann= 5 ,-1 , 0
  4035.2     .05       0  4594.7     .12       0  4801.2     .05       0
  4974.7     .05       0  5050.4     .05       0
Bank Sta=4974.7,5050.4
XS Rating Curve= 0 ,0
Exp/Cntr=0.3,0.1