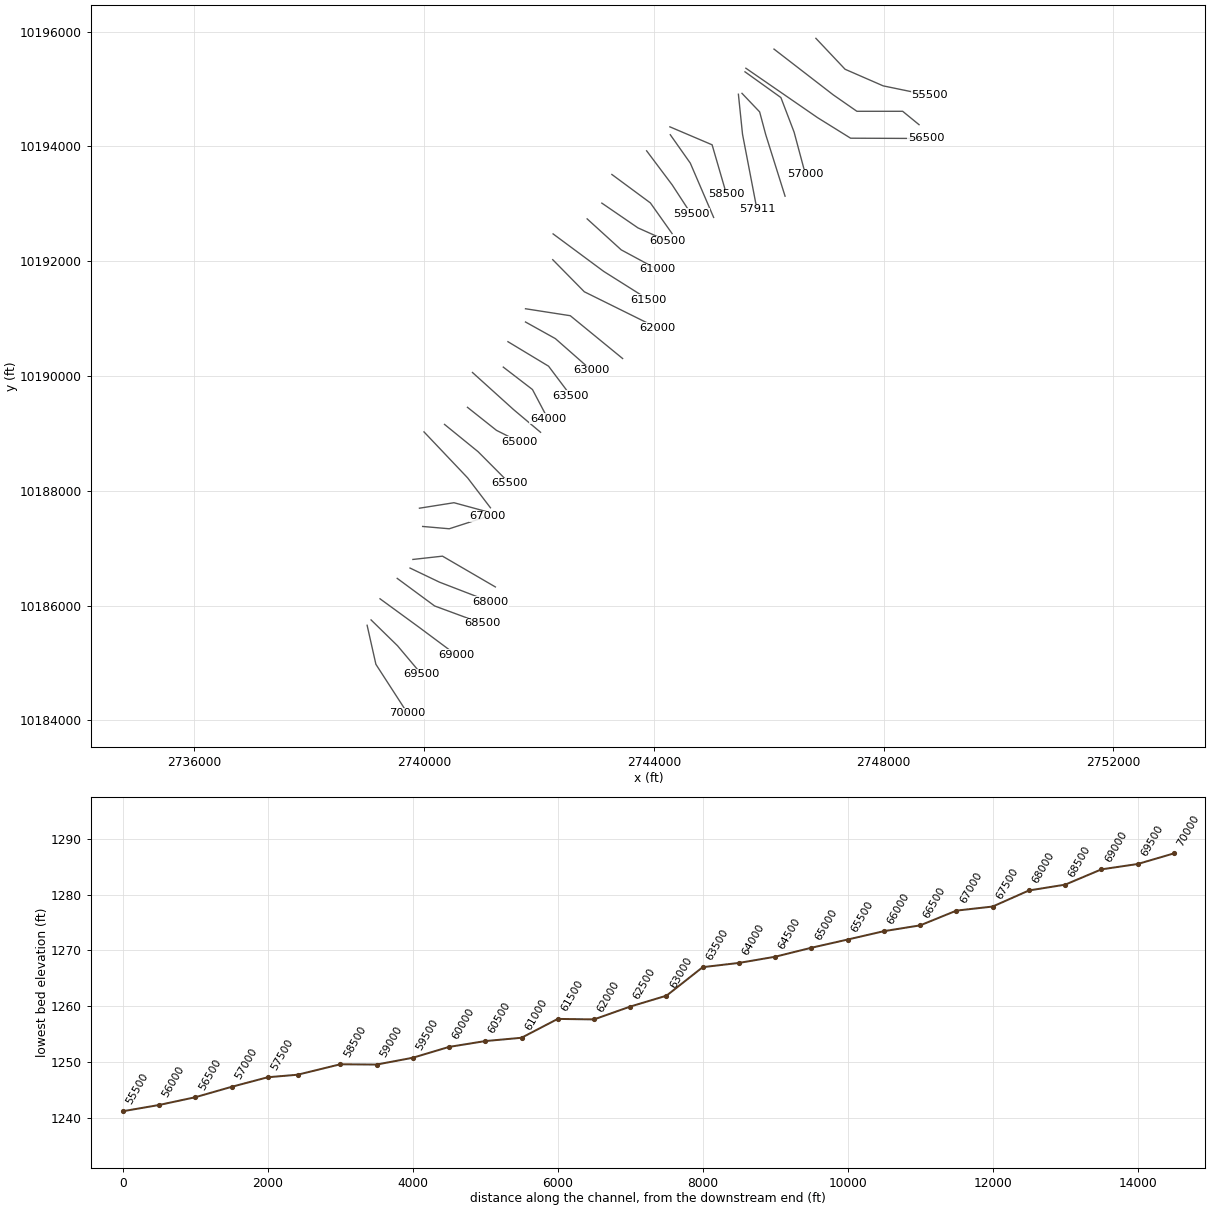
HEC-RAS study HICKORY CREEK.prj: HICKORY CREEK Base Level Engineering

--- HICKORY CREEK.g01 (geometry) --- (continued)

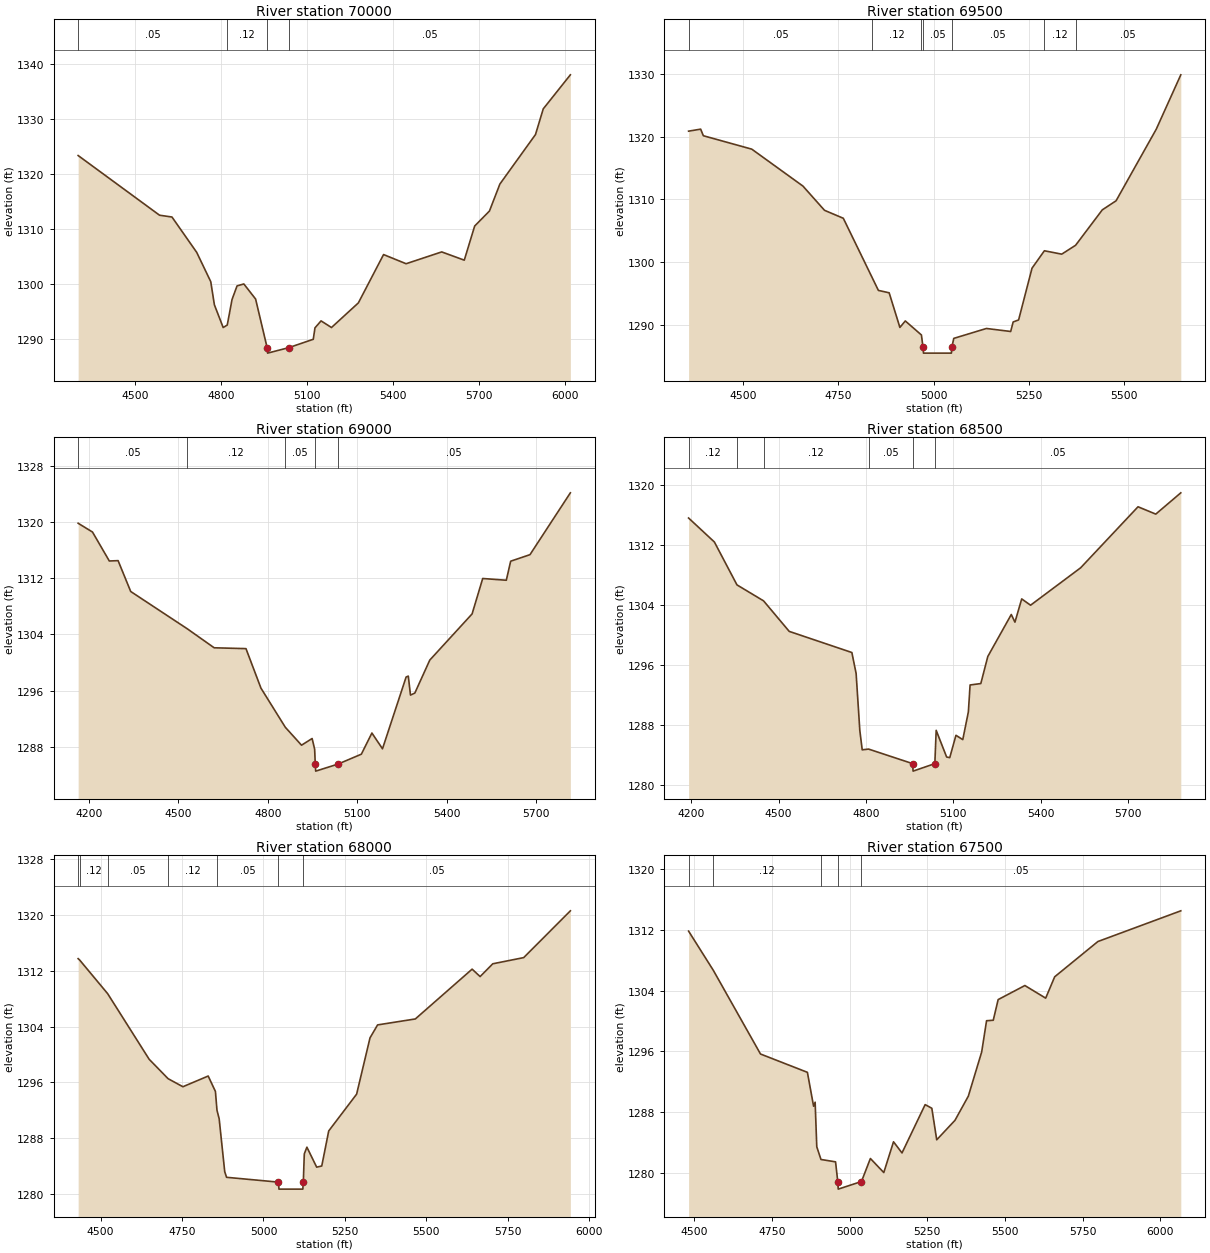
Type RM Length L Ch R = 1 ,70000   ,500,500,500
BEGIN DESCRIPTION:
HICKORY CREEK 140.0
END DESCRIPTION:
XS GIS Cut Line= 3
       2739008.8     10185656.05      2739161.74     10184975.83
      2739713.68     10184121.52
#Sta/Elev= 30
  4302.8 1323.35  4586.3 1312.49  4629.6 1312.16  4715.8 1305.72  4764.6  1300.4
  4777.3 1296.19  4807.9 1292.05  4822.1  1292.5  4838.8 1297.16  4856.3 1299.63
  4879.8 1299.98  4920.8 1297.24    4961 1288.39  4962.5 1287.39  5036.7 1288.39
  5121.7 1289.91  5127.6 1291.99  5148.8 1293.26  5185.1 1292.05  5278.7 1296.53
  5366.5 1305.33    5445 1303.66    5569 1305.81  5647.6 1304.31  5683.8 1310.52
  5735.3 1313.25  5771.6 1318.16  5895.6 1327.17  5922.7 1331.85  6017.1 1338.04
#Mann= 4 ,-1 , 0
  4302.8     .05       0  4822.1     .12       0    4961     .05       0
  5036.7     .05       0
Bank Sta=4961,5036.7
XS Rating Curve= 0 ,0
Exp/Cntr=0.3,0.1

Type RM Length L Ch R = 1 ,69500   ,500,500,500
BEGIN DESCRIPTION:
HICKORY CREEK 139.0
END DESCRIPTION:
XS GIS Cut Line= 3
      2739077.39     10185749.63      2739537.53     10185299.93
      2739955.71     10184803.09
#Sta/Elev= 30
  4356.6 1320.88  4388.3  1321.2  4395.4 1320.15  4522.6 1318.01    4657 1312.12
  4713.6 1308.26    4763 1306.99  4838.8 1297.53  4855.1 1295.49  4883.4 1295.11
  4911.6 1289.59  4925.8 1290.62  4968.2 1288.38  4972.1 1286.49  4973.6 1285.49
  5046.8 1285.49  5048.3 1286.49  5053.1 1287.84  5138.9 1289.42  5202.6 1288.94
  5209.1 1290.46  5223.4 1290.78  5258.6 1299.03  5291.1 1301.81  5336.6 1301.27
    5373 1302.68  5443.2 1308.33  5479.4 1309.78    5585  1321.2  5649.4 1329.86
#Mann= 7 ,-1 , 0
  4356.6     .05       0  4838.8     .12       0  4968.2     .05       0
  4972.1     .05       0  5048.3     .05       0  5291.1     .12       0
    5373     .05       0
Bank Sta=4972.1,5048.3
XS Rating Curve= 0 ,0
Exp/Cntr=0.3,0.1

Type RM Length L Ch R = 1 ,69000   ,500,500,500
BEGIN DESCRIPTION:
HICKORY CREEK 138.0
END DESCRIPTION:
XS GIS Cut Line= 3
      2739233.37     10186117.63      2739908.18     10185624.99
      2740561.39     10185138.78
#Sta/Elev= 30
  4164.5  1319.8  4212.6 1318.55    4269 1314.43  4298.4 1314.48  4340.7 1310.09
  4530.4 1304.78  4620.4 1302.08    4727 1301.96  4777.2 1296.34  4858.9 1290.77
  4913.2 1288.22  4948.7 1289.17  4957.2 1287.65  4959.2 1285.53  4960.7 1284.53
  5035.4 1285.53  5113.7 1286.94  5149.1 1289.95  5184.6 1287.71  5263.8 1297.92
  5271.1 1298.05  5278.4 1295.35    5293 1295.64  5343.1 1300.33  5484.9  1306.9
  5520.5 1311.94  5599.6 1311.69  5614.2  1314.4  5678.9 1315.33  5814.3 1324.13
#Mann= 5 ,-1 , 0
  4164.5     .05       0  4530.4     .12       0  4858.9     .05       0
  4959.2     .03       0  5035.4     .05       0
Bank Sta=4959.2,5035.4
XS Rating Curve= 0 ,0
Exp/Cntr=0.3,0.1

Type RM Length L Ch R = 1 ,68500   ,500,500,500
BEGIN DESCRIPTION:
HICKORY CREEK 137.0
END DESCRIPTION:
XS GIS Cut Line= 3
      2739532.75     10186473.23       2740183.7      10185992.7
      2741009.71     10185687.76
#Sta/Elev= 30
  4190.9 1315.55  4279.5 1312.35    4357 1306.63  4448.3  1304.5  4536.3 1300.43
  4751.4 1297.61    4766 1294.81  4778.7 1287.21  4786.9 1284.63  4808.8 1284.73
    4960 1282.79  4961.5 1281.79  5036.2 1282.79  5040.8 1287.23  5076.7 1283.67
  5087.4 1283.59  5108.7 1286.57  5132.1 1285.99  5151.3  1289.7  5157.2 1293.28
    5194 1293.47    5218 1297.08  5298.6 1302.68  5311.2 1301.66  5334.4 1304.76
  5364.8 1303.92  5536.7 1308.91  5733.7 1317.05  5794.6 1316.07  5880.5 1318.91
#Mann= 6 ,-1 , 0
  4190.9     .12       0    4357     .05       0  4448.3     .12       0
  4808.8     .05       0    4960     .03       0  5036.2     .05       0
Bank Sta=4960,5036.2
XS Rating Curve= 0 ,0
Exp/Cntr=0.3,0.1

Type RM Length L Ch R = 1 ,68000   ,500,500,500
BEGIN DESCRIPTION:
HICKORY CREEK 136.0
END DESCRIPTION:
XS GIS Cut Line= 3
      2739755.65     10186653.13      2740268.81     10186407.09
      2741147.95     10186067.91
#Sta/Elev= 30
  4430.9  1313.7  4435.3 1313.52  4521.6 1308.69  4648.9 1299.32  4707.1 1296.54
  4752.6 1295.39  4830.2 1296.92  4852.4 1294.72  4857.2 1292.03  4863.9 1290.81
    4881 1283.24  4886.6 1282.44    5046 1281.75  5047.5 1280.75  5120.8 1280.75
  5122.3 1281.75  5125.3 1285.78  5133.3 1286.75  5163.3 1283.89  5178.9 1284.06
  5200.3 1289.07    5286 1294.33  5327.1 1302.38  5350.4 1304.23  5466.2 1305.08
  5640.6  1312.2  5665.2 1311.14  5704.1 1312.97    5799 1313.85  5942.3 1320.54
#Mann= 7 ,-1 , 0
  4430.9     .05       0  4435.3     .12       0  4521.6     .05       0
  4707.1     .12       0  4857.2     .05       0    5046     .03       0
  5122.3     .05       0
Bank Sta=5046,5122.3
XS Rating Curve= 0 ,0
Exp/Cntr=0.3,0.1

Type RM Length L Ch R = 1 ,67500   ,500,500,500
BEGIN DESCRIPTION:
HICKORY CREEK 135.0
END DESCRIPTION:
XS GIS Cut Line= 3
      2739805.68     10186803.11      2740320.71     10186860.41
      2741241.36     10186323.85
#Sta/Elev= 30
  4481.8 1311.82  4561.4 1306.66  4713.2 1295.65  4864.1 1293.24    4884 1288.78
    4889 1289.31  4894.3 1283.44  4907.8 1281.77  4954.7 1281.46  4961.8 1278.87
  4963.3 1277.87  5038.1 1278.87  5066.8  1281.9  5109.9 1280.05  5141.2  1284.1
  5168.5 1282.63    5243 1288.99  5264.5 1288.51  5280.2 1284.36  5338.9 1286.92
  5381.9  1290.1  5424.9 1295.92  5440.6 1300.03  5462.1 1300.09  5477.9 1302.81
  5563.9 1304.66  5630.8    1303  5659.8 1305.81  5798.8 1310.45  6065.6 1314.49
#Mann= 5 ,-1 , 0
  4481.8     .05       0  4561.4     .12       0  4907.8     .05       0
  4961.8     .03       0  5038.1     .05       0
Bank Sta=4961.8,5038.1
XS Rating Curve= 0 ,0
Exp/Cntr=0.3,0.1

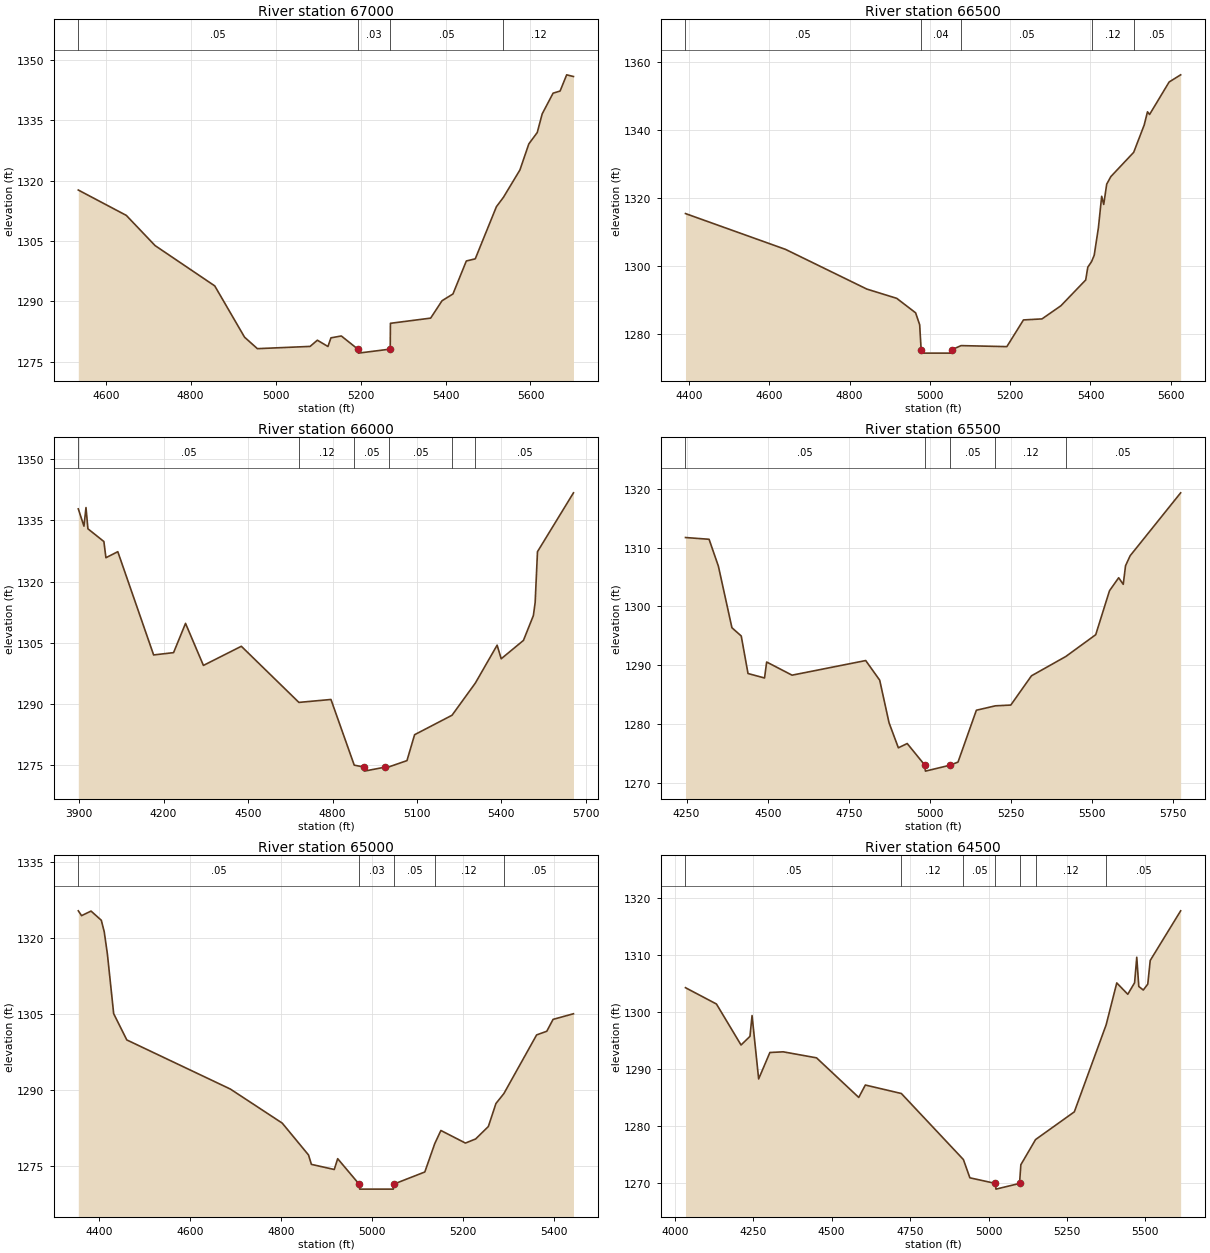
Type RM Length L Ch R = 1 ,67000   ,500,500,500
BEGIN DESCRIPTION:
HICKORY CREEK 134.0
END DESCRIPTION:
XS GIS Cut Line= 3
      2739975.71      10187377.7      2740438.46     10187337.45
      2741105.67     10187553.11
#Sta/Elev= 30
  4535.5 1317.67  4648.5 1311.37  4716.2 1303.87  4856.7 1293.85  4926.9  1281.1
  4957.1 1278.25  5081.2 1278.81  5098.3 1280.35  5123.2 1278.79  5130.3 1280.94
  5154.7  1281.4  5193.5 1278.14    5195 1277.14  5269.8 1278.14  5270.3 1284.55
    5365 1285.84  5391.8 1290.16  5417.5 1291.84    5449 1300.04    5470 1300.57
  5519.8 1313.53  5536.3 1315.86  5575.1 1322.65  5596.1 1329.13  5615.9 1331.96
  5627.6  1336.6  5653.2 1341.74  5669.7 1342.27  5685.2  1346.3  5701.2 1345.88
#Mann= 4 ,-1 , 0
  4535.5     .05       0  5193.5     .03       0  5269.8     .05       0
  5536.3     .12       0
Bank Sta=5193.5,5269.8
XS Rating Curve= 0 ,0
Exp/Cntr=0.3,0.1

Type RM Length L Ch R = 1 ,66500   ,500,500,500
BEGIN DESCRIPTION:
HICKORY CREEK 133.0
END DESCRIPTION:
XS GIS Cut Line= 3
      2739919.58     10187695.84      2740520.75     10187791.29
      2741123.42     10187627.23
#Sta/Elev= 30
  4391.3 1315.53  4640.5    1305    4843 1293.33  4917.4 1290.61  4964.5 1286.35
  4974.6 1282.82  4978.2  1275.5  4979.7  1274.5  5053.1  1274.5  5054.6  1275.5
  5077.7 1276.71  5191.7 1276.41  5233.1 1284.26  5279.2 1284.56  5326.4 1288.43
  5388.1 1296.01  5393.3 1299.76  5402.7  1301.4  5409.3 1303.28  5419.7 1311.31
  5427.9 1320.61    5433 1318.21  5440.4 1324.18  5450.8 1326.41  5507.6 1333.53
  5533.7 1341.54    5542 1345.45  5547.2 1344.66  5595.9 1354.21  5624.6 1356.32
#Mann= 5 ,-1 , 0
  4391.3     .05       0  4978.2     .04       0  5077.7     .05       0
  5402.7     .12       0  5507.6     .05       0
Bank Sta=4978.2,5054.6
XS Rating Curve= 0 ,0
Exp/Cntr=0.3,0.1

Type RM Length L Ch R = 1 ,66000   ,500,500,500
BEGIN DESCRIPTION:
HICKORY CREEK 132.0
END DESCRIPTION:
XS GIS Cut Line= 3
        2739999.     10189024.93      2740757.94     10188224.68
      2741155.67     10187703.13
#Sta/Elev= 30
  3897.1 1337.84  3917.2  1333.6  3924.4 1338.16  3931.3 1332.95    3988 1329.82
  3995.2 1325.85  4037.4 1327.33  4164.7 1301.98  4235.5 1302.55    4278 1309.73
  4341.5 1299.41  4476.2 1304.11  4680.7 1290.33  4794.5 1291.05  4877.2 1274.93
  4911.6 1274.46  4913.1 1273.46  4988.2 1274.46  5002.3 1274.55  5064.5 1276.04
  5091.6  1282.4  5224.6 1287.18  5307.4 1295.08  5384.7 1304.38  5399.2 1301.04
  5478.2 1305.55  5513.5 1311.65  5519.8 1314.84  5528.1 1327.33  5655.9 1341.78
#Mann= 6 ,-1 , 0
  3897.1     .05       0  4680.7     .12       0  4877.2     .05       0
  5002.3     .05       0  5224.6     .12       0  5307.4     .05       0
Bank Sta=4911.6,4988.2
XS Rating Curve= 0 ,0
Exp/Cntr=0.3,0.1

Type RM Length L Ch R = 1 ,65500   ,500,500,500
BEGIN DESCRIPTION:
HICKORY CREEK 131.0
END DESCRIPTION:
XS GIS Cut Line= 3
      2740356.18     10189155.52       2740940.6     10188680.07
      2741485.24     10188132.51
#Sta/Elev= 30
  4246.6 1311.74  4319.3 1311.44    4348 1306.86  4389.7 1296.38  4418.4 1294.97
  4439.3 1288.58  4490.2 1287.82  4496.7 1290.54    4575  1288.3  4801.9 1290.79
    4845 1287.45  4873.8  1280.2  4902.5 1275.93  4929.8 1276.66  4984.3 1272.96
  4985.8 1271.96    5061 1272.96  5086.3  1273.5  5142.9 1282.33  5201.6 1283.08
  5248.9 1283.21  5312.6 1288.19  5418.4 1291.48  5510.6 1295.19    5553 1302.67
  5581.3 1304.89  5595.4 1303.77  5602.5 1306.94  5616.6 1308.63  5772.3 1319.35
#Mann= 5 ,-1 , 0
  4246.6     .05       0  4984.3     .05       0    5061     .05       0
  5201.6     .12       0  5418.4     .05       0
Bank Sta=4984.3,5061
XS Rating Curve= 0 ,0
Exp/Cntr=0.3,0.1

Type RM Length L Ch R = 1 ,65000   ,500,500,500
BEGIN DESCRIPTION:
HICKORY CREEK 130.0
END DESCRIPTION:
XS GIS Cut Line= 3
      2740755.68     10189453.12      2741260.94     10189051.72
      2741655.69     10188853.11
#Sta/Elev= 30
  4354.7 1325.35  4361.9  1324.4  4382.7  1325.3  4405.2 1323.49  4411.6 1321.24
  4418.6 1316.83  4432.4 1305.07  4461.2  1299.9  4688.7 1290.21  4802.5  1283.5
  4860.2 1277.22  4866.5 1275.37  4916.7 1274.36  4924.2 1276.49  4971.1 1271.49
  4972.6 1270.49  5046.3 1270.49  5047.8 1271.49  5115.5 1273.87  5137.3 1279.45
  5150.8 1282.05  5204.7 1279.57  5227.1 1280.38    5255 1282.83  5271.7 1287.37
    5289 1289.31    5361 1300.89  5383.3 1301.61  5397.1 1303.95  5441.9 1305.06
#Mann= 5 ,-1 , 0
  4354.7     .05       0  4971.1     .03       0  5047.8     .05       0
  5137.3     .12       0    5289     .05       0
Bank Sta=4971.1,5047.8
XS Rating Curve= 0 ,0
Exp/Cntr=0.3,0.1

Type RM Length L Ch R = 1 ,64500   ,500,500,500
BEGIN DESCRIPTION:
HICKORY CREEK 129.0
END DESCRIPTION:
XS GIS Cut Line= 3
      2740842.77     10190059.99      2741559.46     10189412.45
      2742027.99     10189018.25
#Sta/Elev= 30
  4034.1 1304.31  4132.8 1301.44  4211.2 1294.23  4239.6 1295.75  4246.3 1299.41
  4267.3 1288.26  4303.1 1292.91  4345.7 1293.03  4451.8 1291.97  4586.3 1285.01
  4607.3 1287.19  4722.1  1285.7  4919.9 1274.08  4940.5 1270.87  5022.1 1269.88
  5023.6 1268.88  5098.8 1269.88    5103 1273.17  5149.9  1277.6  5273.4 1282.47
  5374.9 1297.79  5408.7 1305.15  5443.8 1303.15  5465.5 1305.18  5472.4 1309.67
  5478.9 1304.52  5493.2  1303.9  5507.5 1304.94  5515.3  1309.1  5612.3 1317.83
#Mann= 7 ,-1 , 0
  4034.1     .05       0  4722.1     .12       0  4919.9     .05       0
  5022.1     .03       0  5098.8     .05       0  5149.9     .12       0
  5374.9     .05       0
Bank Sta=5022.1,5098.8
XS Rating Curve= 0 ,0
Exp/Cntr=0.3,0.1

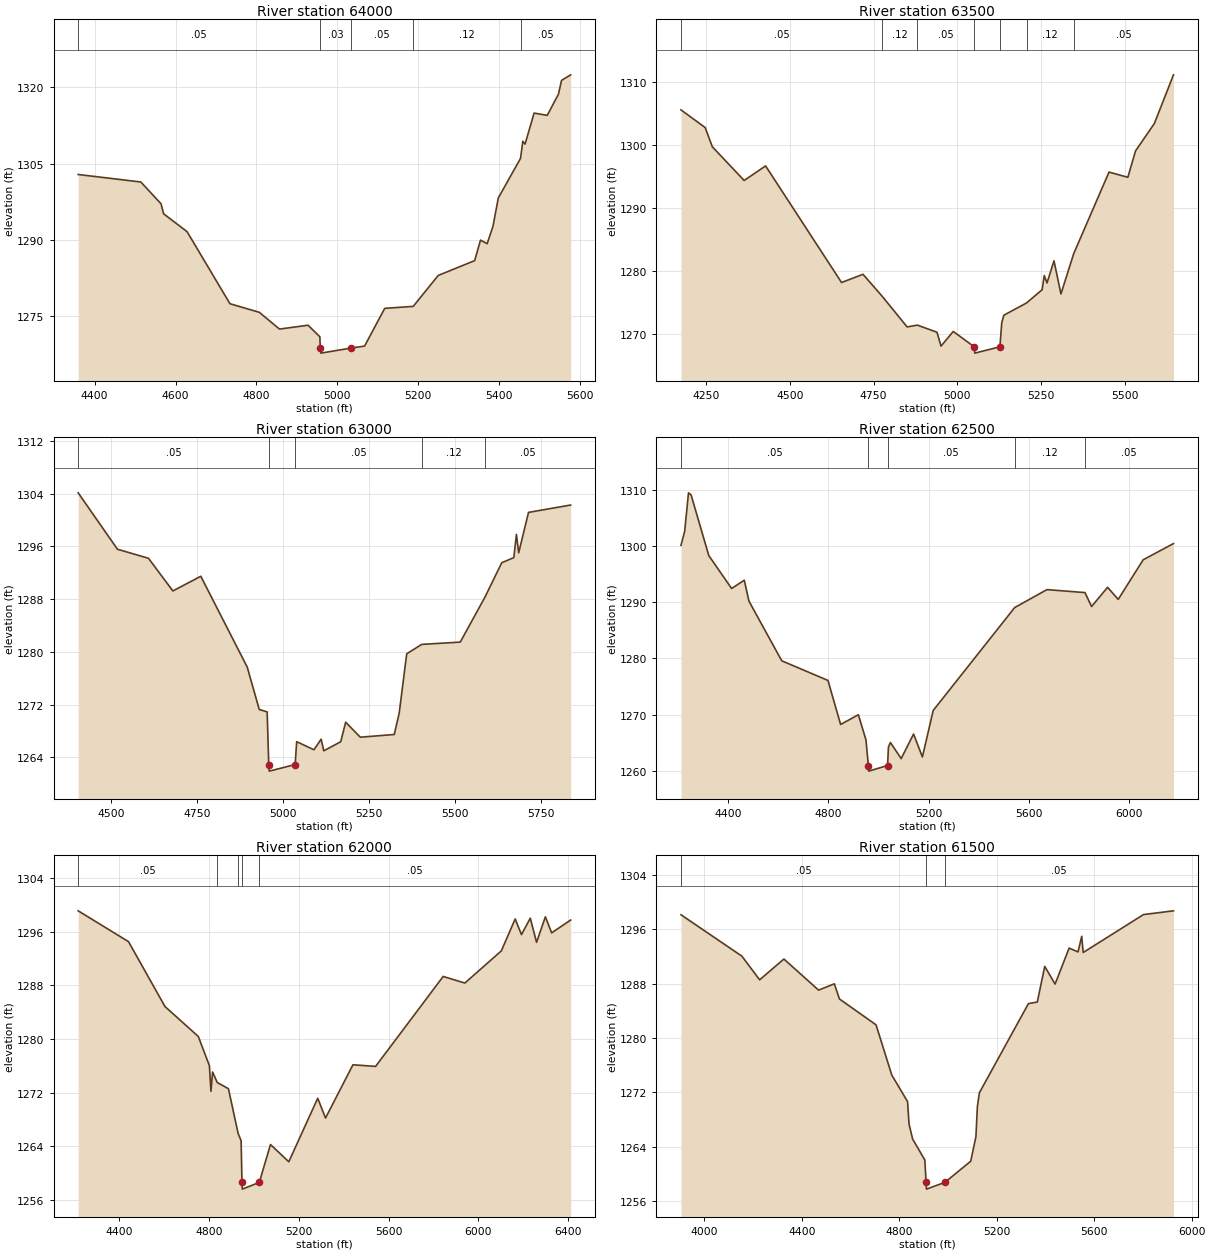
Type RM Length L Ch R = 1 ,64000   ,500,500,500
BEGIN DESCRIPTION:
HICKORY CREEK 128.0
END DESCRIPTION:
XS GIS Cut Line= 3
       2741379.2     10190153.58      2741887.03     10189763.11
      2742155.67     10189253.14
#Sta/Elev= 30
  4359.4 1302.84  4514.3 1301.37  4564.2 1297.09  4570.5 1295.13  4628.5 1291.62
  4734.5 1277.47  4807.1 1275.78  4856.9 1272.49  4927.5 1273.25  4956.6 1270.98
  4957.6 1268.77  4959.1 1267.77  5034.3 1268.77  5067.2 1269.15  5116.9 1276.56
  5187.4 1276.95  5249.1 1283.02  5339.1 1285.93  5353.6 1289.96    5370 1289.26
  5384.3 1292.64  5397.6 1298.24  5452.5 1306.01  5458.1 1309.36  5463.7 1308.81
    5486  1314.9  5518.5 1314.45  5546.2 1318.61  5553.8 1321.31  5576.4 1322.41
#Mann= 5 ,-1 , 0
  4359.4     .05       0  4957.6     .03       0  5034.3     .05       0
  5187.4     .12       0  5452.5     .05       0
Bank Sta=4957.6,5034.3
XS Rating Curve= 0 ,0
Exp/Cntr=0.3,0.1

Type RM Length L Ch R = 1 ,63500   ,500,500,500
BEGIN DESCRIPTION:
HICKORY CREEK 127.0
END DESCRIPTION:
XS GIS Cut Line= 3
      2741460.33     10190596.45      2742167.28     10190169.64
       2742555.7     10189653.08
#Sta/Elev= 30
  4174.2 1305.52  4246.5 1302.72  4267.9 1299.68    4363 1294.34  4427.1 1296.65
  4654.1 1278.19  4718.2 1279.49  4776.1 1275.98  4850.1 1271.16  4880.9 1271.44
  4939.4 1270.32  4951.4 1268.12    4988 1270.44  5050.8 1268.01  5052.3 1267.01
  5127.5 1268.01  5132.9  1271.8  5139.2 1273.01    5207 1274.95  5253.7 1277.05
    5260 1279.29  5268.3 1278.12  5289.1 1281.62  5309.9 1276.38  5347.9 1282.74
  5453.6 1295.67  5509.9 1294.85  5532.8 1299.02    5589 1303.35  5646.3 1311.07
#Mann= 7 ,-1 , 0
  4174.2     .05       0  4776.1     .12       0  4880.9     .05       0
  5050.8     .03       0  5127.5     .05       0    5207     .12       0
  5347.9     .05       0
Bank Sta=5050.8,5127.5
XS Rating Curve= 0 ,0
Exp/Cntr=0.3,0.1

Type RM Length L Ch R = 1 ,63000   ,500,500,500
BEGIN DESCRIPTION:
HICKORY CREEK 126.0
END DESCRIPTION:
XS GIS Cut Line= 3
      2741765.94     10190939.57      2742285.75     10190650.04
      2742913.36     10190097.77
#Sta/Elev= 30
    4405 1304.13  4519.2 1295.57  4609.3  1294.2  4680.2 1289.24  4761.3 1291.47
  4896.2 1277.69  4931.2 1271.25  4954.1 1270.89  4958.8  1262.9  4960.3  1261.9
  5035.5  1262.9  5039.9 1266.37  5090.1 1265.14    5111 1266.75  5118.6 1264.98
  5167.9 1266.36  5182.2 1269.32  5224.8 1267.05  5323.5 1267.46  5337.8 1270.71
  5359.6  1279.7  5403.2 1281.13  5515.2 1281.48  5587.4 1288.35  5635.7 1293.52
  5670.8  1294.3  5678.4 1297.82    5685 1295.03  5713.5 1301.16    5836 1302.28
#Mann= 5 ,-1 , 0
    4405     .05       0  4958.8     .05       0  5035.5     .05       0
  5403.2     .12       0  5587.4     .05       0
Bank Sta=4958.8,5035.5
XS Rating Curve= 0 ,0
Exp/Cntr=0.3,0.1

Type RM Length L Ch R = 1 ,62500   ,500,500,500
BEGIN DESCRIPTION:
HICKORY CREEK 125.0
END DESCRIPTION:
XS GIS Cut Line= 3
      2741765.99     10191170.35      2742545.42      10191049.1
      2743456.46     10190303.26
#Sta/Elev= 30
  4211.2 1300.09  4225.9 1302.56  4241.2 1309.41  4251.4 1309.06  4322.2 1298.26
  4413.3 1292.41  4463.9 1293.88  4482.5 1290.17  4613.4 1279.56  4797.9 1276.07
  4848.5 1268.24  4919.3 1269.97  4949.7 1265.49  4959.3 1260.95  4960.8 1259.95
    5036 1260.95  5039.4 1264.24  5047.2 1265.04  5090.3 1262.18  5139.8 1266.54
    5175 1262.47  5218.1 1270.73  5543.4 1289.02  5672.4 1292.21    5824 1291.68
  5850.4  1289.2  5914.3 1292.62  5956.7 1290.47  6056.4 1297.51  6177.4 1300.39
#Mann= 5 ,-1 , 0
  4211.2     .05       0  4959.3     .03       0    5036     .05       0
  5543.4     .12       0    5824     .05       0
Bank Sta=4959.3,5036
XS Rating Curve= 0 ,0
Exp/Cntr=0.3,0.1

Type RM Length L Ch R = 1 ,62000   ,500,500,500
BEGIN DESCRIPTION:
HICKORY CREEK 124.0
END DESCRIPTION:
XS GIS Cut Line= 3
      2742240.05     10192024.94      2742789.83     10191466.01
      2744055.24     10190839.76
#Sta/Elev= 30
    4216 1299.08  4440.5 1294.49  4603.1 1284.83  4751.6 1280.38  4801.1 1276.03
  4808.1 1272.22  4815.3 1275.09  4836.2 1273.52    4886  1272.6  4929.3 1265.93
  4942.6 1264.85  4946.3 1258.65  4947.8 1257.65  5023.6 1258.65  5073.5 1264.29
  5155.1 1261.72  5284.1 1271.18  5318.9 1268.23  5441.1 1276.16  5542.1 1275.92
  5843.4 1289.31  5940.2 1288.33  6102.8 1293.12  6164.5 1297.87  6192.5 1295.54
  6231.8 1297.98  6259.8 1294.39  6299.1 1298.19  6327.1  1295.8  6411.9 1297.71
#Mann= 5 ,-1 , 0
    4216     .05       0  4836.2     .12       0  4929.3     .05       0
  4946.3     .05       0  5023.6     .05       0
Bank Sta=4946.3,5023.6
XS Rating Curve= 0 ,0
Exp/Cntr=0.3,0.1

Type RM Length L Ch R = 1 ,61500   ,500,500,500
BEGIN DESCRIPTION:
HICKORY CREEK 123.0
END DESCRIPTION:
XS GIS Cut Line= 3
      2742246.28     10192474.09      2743126.94     10191821.17
      2743909.82     10191327.56
#Sta/Elev= 30
  3903.7 1298.15  4153.5 1292.06  4226.6 1288.57  4326.2 1291.63  4468.6 1287.05
  4533.3 1287.98  4554.1 1285.75  4704.4 1281.94  4769.1 1274.54  4833.8 1270.63
    4840  1267.3  4854.6 1265.12  4904.7 1262.03  4909.9 1258.74  4911.4 1257.74
  4987.3 1258.74  5093.1 1261.85  5114.5 1265.47  5120.4 1269.87  5128.6 1271.93
    5330 1285.06  5366.4  1285.3    5397 1290.55  5439.4 1287.94  5497.1 1293.24
  5533.6 1292.68  5548.8 1294.98  5554.8 1292.59  5802.4 1298.18  5925.5 1298.73
#Mann= 3 ,-1 , 0
  3903.7     .05       0  4909.9     .03       0  4987.3     .05       0
Bank Sta=4909.9,4987.3
XS Rating Curve= 0 ,0
Exp/Cntr=0.3,0.1

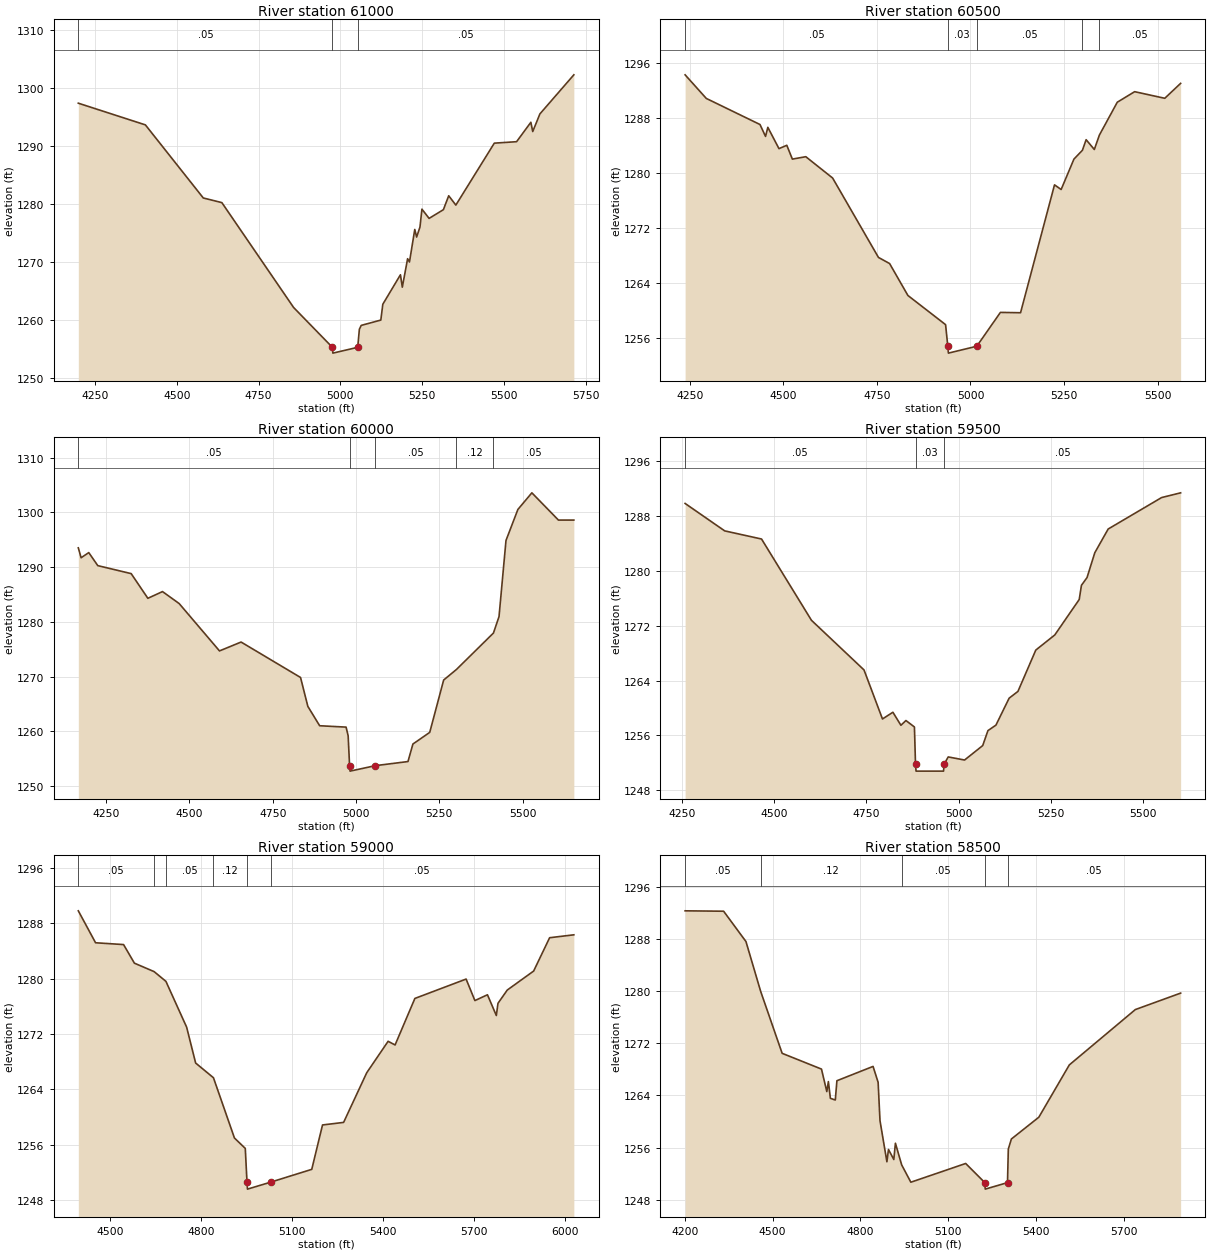
Type RM Length L Ch R = 1 ,61000   ,500,500,500
BEGIN DESCRIPTION:
HICKORY CREEK 122.0
END DESCRIPTION:
XS GIS Cut Line= 3
      2742838.88     10192736.08       2743431.4     10192196.78
      2744059.65     10191857.53
#Sta/Elev= 30
  4198.8 1297.45  4403.9 1293.71  4580.9 1281.11  4637.7 1280.31  4857.1 1262.23
  4975.7 1255.36  4977.2 1254.36  5053.1 1255.36  5058.2 1258.48  5063.9 1259.14
  5123.8 1260.06  5129.9 1262.79  5183.8 1267.87  5189.5 1265.73  5205.7 1270.64
  5211.4 1270.07  5227.6 1275.68  5233.3 1274.37  5243.5  1276.1  5249.5 1279.18
  5271.4 1277.59  5315.1 1279.09  5331.4 1281.49  5353.2 1279.88  5470.8 1290.56
  5538.9 1290.81  5582.6 1294.16  5588.3 1292.56  5610.2  1295.6    5714 1302.34
#Mann= 3 ,-1 , 0
  4198.8     .05       0  4975.7     .03       0  5053.1     .05       0
Bank Sta=4975.7,5053.1
XS Rating Curve= 0 ,0
Exp/Cntr=0.3,0.1

Type RM Length L Ch R = 1 ,60500   ,500,500,500
BEGIN DESCRIPTION:
HICKORY CREEK 121.0
END DESCRIPTION:
XS GIS Cut Line= 3
       2743094.6     10193010.57      2743723.52     10192579.08
      2744236.19     10192349.32
#Sta/Elev= 30
  4237.3 1294.22  4293.9 1290.79  4437.4    1287  4452.3 1285.27  4458.4 1286.59
  4488.2 1283.49  4509.1 1283.98    4524 1281.97  4559.9 1282.32  4631.6 1279.22
  4754.1 1267.68  4783.9 1266.79  4832.8 1262.15  4933.5 1257.91  4939.5 1254.77
    4941 1253.77  5016.9 1254.77  5080.1 1259.69  5133.9 1259.64  5224.7 1278.23
  5242.4 1277.55  5276.6 1281.97  5299.2 1283.25  5309.2 1284.79  5331.1 1283.37
  5344.6 1285.46  5392.5 1290.24  5438.9 1291.77  5519.4 1290.81  5561.8 1292.98
#Mann= 5 ,-1 , 0
  4237.3     .05       0  4939.5     .03       0  5016.9     .05       0
  5299.2     .12       0  5344.6     .05       0
Bank Sta=4939.5,5016.9
XS Rating Curve= 0 ,0
Exp/Cntr=0.3,0.1

Type RM Length L Ch R = 1 ,60000   ,500,500,500
BEGIN DESCRIPTION:
HICKORY CREEK 120.0
END DESCRIPTION:
XS GIS Cut Line= 3
      2743269.27      10193509.6      2743939.67     10193014.01
      2744317.29     10192480.29
#Sta/Elev= 30
  4166.3 1293.51  4174.7  1291.7  4197.7 1292.64  4224.8 1290.26    4325  1288.8
  4375.1 1284.29    4419 1285.52  4469.1 1283.33  4590.1 1274.68  4654.9  1276.3
  4833.4 1269.83  4855.3 1264.55  4890.8 1261.01  4970.1 1260.76  4976.3 1259.17
  4980.6 1253.72  4982.1 1252.72    5058 1253.72  5155.9 1254.47  5170.7 1257.67
  5221.2  1259.8    5263 1269.36  5301.4 1271.29  5412.5 1277.95  5429.2 1280.95
  5450.1 1294.85  5485.8 1300.52  5527.8 1303.56  5607.6 1298.58  5653.8 1298.58
#Mann= 5 ,-1 , 0
  4166.3     .05       0  4980.6     .03       0    5058     .05       0
  5301.4     .12       0  5412.5     .05       0
Bank Sta=4980.6,5058
XS Rating Curve= 0 ,0
Exp/Cntr=0.3,0.1

Type RM Length L Ch R = 1 ,59500   ,500,500,500
BEGIN DESCRIPTION:
HICKORY CREEK 119.0
END DESCRIPTION:
XS GIS Cut Line= 3
      2743874.36     10193921.31      2744319.17     10193328.16
       2744647.9     10192823.37
#Sta/Elev= 30
  4258.6 1289.83  4365.9 1285.83  4465.9 1284.64  4601.3 1272.78  4743.8 1265.54
  4793.8 1258.39  4822.1 1259.37  4843.8 1257.47  4857.5 1258.16  4880.5 1257.22
  4883.4 1251.78  4884.9 1250.78  4959.4 1250.78  4960.9 1251.78  4972.1 1252.85
  5016.5  1252.4  5065.7 1254.51  5079.8 1256.69  5101.5 1257.49  5137.3 1261.42
  5161.2 1262.41  5209.6 1268.44    5261 1270.64  5327.4 1275.82  5333.4 1277.89
  5348.5 1279.01  5369.6 1282.64  5405.9  1286.1  5550.8 1290.69  5602.4 1291.38
#Mann= 3 ,-1 , 0
  4258.6     .05       0  4883.4     .03       0  4960.9     .05       0
Bank Sta=4883.4,4960.9
XS Rating Curve= 0 ,0
Exp/Cntr=0.3,0.1

Type RM Length L Ch R = 1 ,59000   ,500,500,500
BEGIN DESCRIPTION:
HICKORY CREEK 118.0
END DESCRIPTION:
XS GIS Cut Line= 3
      2744286.06     10194202.02      2744634.72     10193706.86
      2745040.77     10192761.26
#Sta/Elev= 30
  4394.4 1289.81  4451.3 1285.19  4543.7 1284.93  4579.4 1282.24  4644.4 1281.02
  4683.4 1279.61  4751.8 1272.98  4781.4  1267.8  4840.2 1265.67  4909.5 1256.95
  4945.2 1255.45  4950.9 1250.56  4952.4 1249.56  5028.4 1250.56  5164.5 1252.42
    5200 1258.84  5269.6 1259.21  5345.7 1266.38  5416.4 1270.94  5439.4 1270.41
  5504.7 1277.14  5673.7 1279.94  5702.7 1276.83  5744.1 1277.67  5773.4 1274.67
  5778.8 1276.43  5809.4 1278.35  5896.5  1281.1  5949.2 1285.92  6029.1 1286.34
#Mann= 6 ,-1 , 0
  4394.4     .05       0  4644.4     .12       0  4683.4     .05       0
  4840.2     .12       0  4950.9     .05       0  5028.4     .05       0
Bank Sta=4950.9,5028.4
XS Rating Curve= 0 ,0
Exp/Cntr=0.3,0.1

Type RM Length L Ch R = 1 ,58500   ,589,589,589
BEGIN DESCRIPTION:
HICKORY CREEK 117.0
END DESCRIPTION:
XS GIS Cut Line= 3
      2744279.07     10194339.43      2745014.24     10194026.24
      2745263.37     10193167.86
#Sta/Elev= 30
  4200.9 1292.36  4332.5  1292.3  4408.8 1287.64    4459 1279.99  4532.4 1270.47
  4666.8 1268.05    4685 1264.59  4690.4 1266.13  4697.2 1263.56    4714  1263.3
  4719.5 1266.26    4843 1268.46  4860.3 1266.02  4866.7 1260.13  4890.3 1253.81
  4895.7  1255.7  4913.9 1254.16  4919.4 1256.66  4940.8 1253.33  4972.1 1250.67
  5159.4 1253.55  5224.8 1250.61  5226.3 1249.61  5302.3 1250.61  5305.1 1255.77
  5315.6 1257.31  5409.4 1260.66  5513.5 1268.69    5739 1277.19  5893.8 1279.72
#Mann= 5 ,-1 , 0
  4200.9     .05       0    4459     .12       0  4940.8     .05       0
  5224.8     .03       0  5302.3     .05       0
Bank Sta=5224.8,5302.3
XS Rating Curve= 0 ,0
Exp/Cntr=0.3,0.1

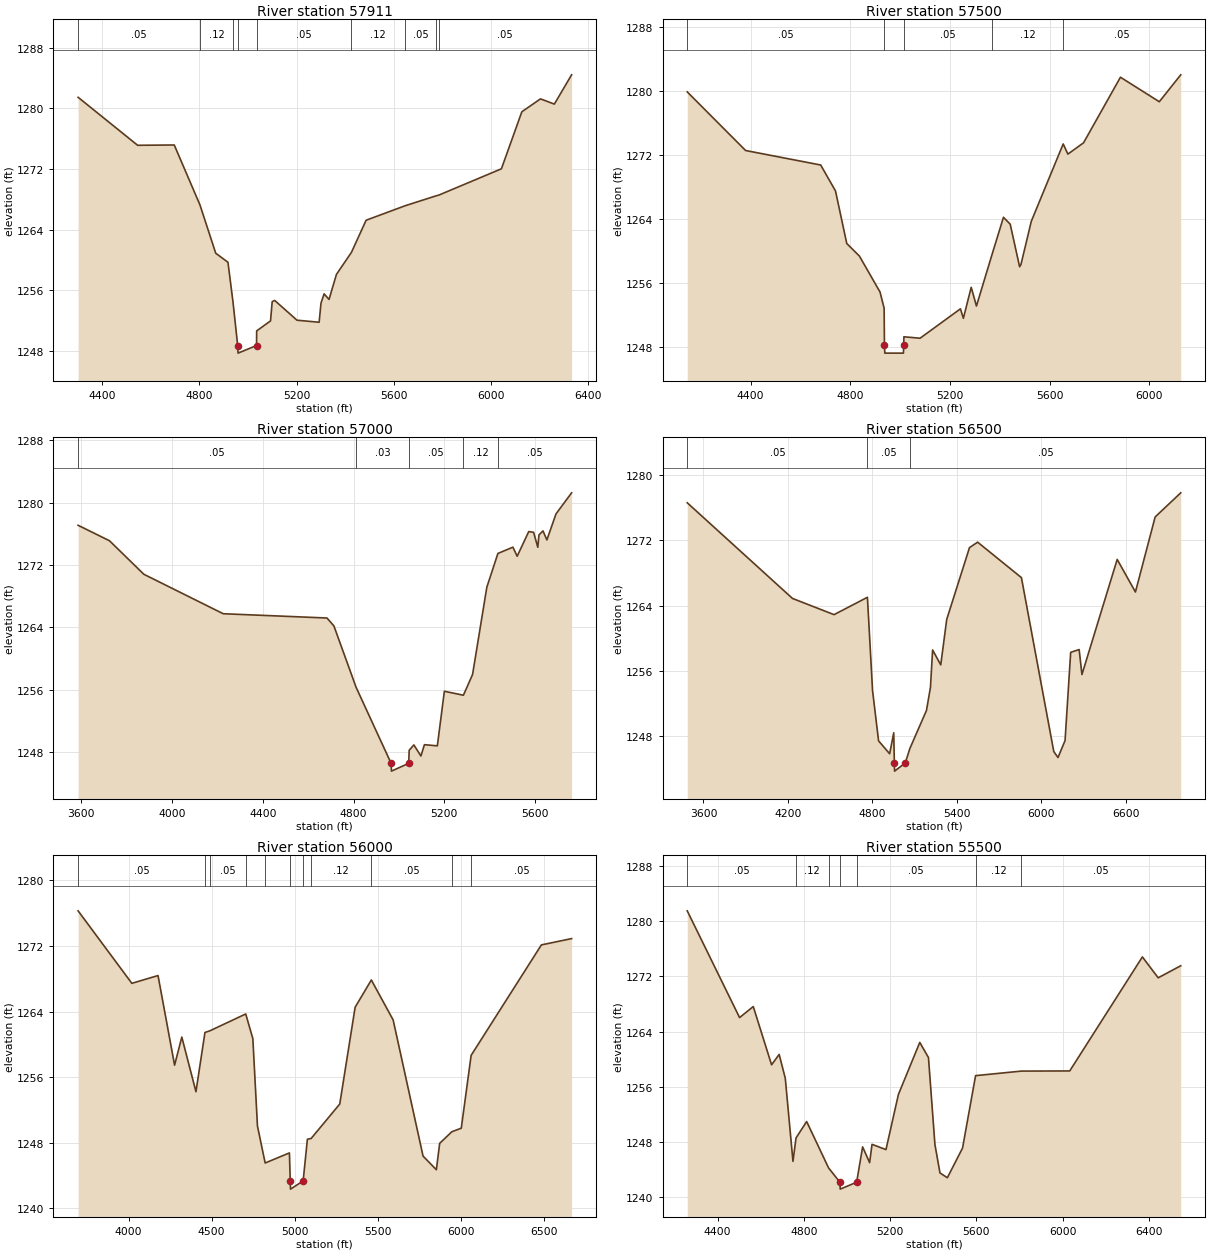
Type RM Length L Ch R = 1 ,57911   ,411,411,411
BEGIN DESCRIPTION:
HICKORY CREEK 116.0
END DESCRIPTION:
XS GIS Cut Line= 3
       2745471.8     10194907.12       2745543.5       10194211.
      2745794.72     10192901.89
#Sta/Elev= 30
  4300.2 1281.47  4545.5 1275.14  4696.3 1275.18  4802.1 1267.29  4867.2 1260.91
  4917.5 1259.72  4938.2 1254.51  4957.6 1248.74  4959.1 1247.74  5035.2 1248.74
  5035.8 1250.67  5092.9 1251.99  5099.7 1254.52  5109.9 1254.69  5201.9 1252.08
  5293.1 1251.81  5300.8 1254.34  5313.5 1255.55  5333.9 1254.82  5364.4 1258.12
  5426.1 1261.02  5486.6 1265.26  5647.4 1267.17  5775.3 1268.48  5786.6 1268.58
  6043.9 1272.04  6128.1 1279.56    6205 1281.26    6262 1280.57    6333 1284.43
#Mann= 9 ,-1 , 0
  4300.2     .05       0  4802.1     .12       0  4938.2     .05       0
  4957.6     .03       0  5035.2     .05       0  5426.1     .12       0
  5647.4     .05       0  5775.3     .12       0  5786.6     .05       0
Bank Sta=4957.6,5035.2
XS Rating Curve= 0 ,0
Exp/Cntr=0.3,0.1

Type RM Length L Ch R = 1 ,57500   ,500,500,500
BEGIN DESCRIPTION:
HICKORY CREEK 115.0
END DESCRIPTION:
XS GIS Cut Line= 4
      2745534.29     10194922.76      2745841.59     10194599.84
      2745947.09     10194204.96       2746284.3     10193131.06
#Sta/Elev= 30
  4145.5 1279.91  4379.7 1272.59    4681 1270.78  4740.4 1267.54  4785.6 1260.98
  4836.3 1259.41  4919.1 1254.92  4935.5  1252.9  4936.8 1248.29  4938.3 1247.29
  5012.9 1247.29  5014.4 1248.29  5014.8 1249.33  5079.7 1249.15  5241.7 1252.82
  5253.5 1251.64  5284.9 1255.51  5305.9 1253.17  5369.6 1259.72  5414.3 1264.25
  5441.4 1263.39  5479.1 1258.08  5484.3 1258.33    5526 1263.75    5654 1273.41
  5672.8 1272.14  5735.6 1273.55  5883.7 1281.74  6039.6 1278.68  6125.6 1282.04
#Mann= 5 ,-1 , 0
  4145.5     .05       0  4936.8     .03       0  5014.4     .05       0
  5369.6     .12       0    5654     .05       0
Bank Sta=4936.8,5014.4
XS Rating Curve= 0 ,0
Exp/Cntr=0.3,0.1

Type RM Length L Ch R = 1 ,57000   ,500,500,500
BEGIN DESCRIPTION:
HICKORY CREEK 114.0
END DESCRIPTION:
XS GIS Cut Line= 4
      2745586.35     10195297.78      2746211.38     10194849.84
       2746441.5     10194246.93      2746638.45     10193511.34
#Sta/Elev= 30
  3585.7 1277.09  3724.4  1275.1  3875.5 1270.81  4225.5 1265.75    4683  1265.2
  4713.5 1264.19  4811.4 1256.32  4965.8 1246.57  4967.3 1245.57  5043.4 1246.57
  5045.4 1248.24  5066.1 1248.93  5097.1 1247.51  5112.7 1248.96  5169.6 1248.81
  5200.6 1255.81  5284.5  1255.3  5324.9 1257.96  5387.8 1269.15  5436.7 1273.48
  5502.8 1274.28  5521.6 1273.12  5572.5 1276.28    5594 1276.19  5612.5 1274.27
  5617.7 1275.85  5635.4 1276.37  5652.6 1275.21  5692.6 1278.54  5761.5 1281.25
#Mann= 5 ,-1 , 0
  3585.7     .05       0  4811.4     .03       0  5043.4     .05       0
  5284.5     .12       0  5436.7     .05       0
Bank Sta=4965.8,5043.4
XS Rating Curve= 0 ,0
Exp/Cntr=0.3,0.1

Type RM Length L Ch R = 1 ,56500   ,500,500,500
BEGIN DESCRIPTION:
HICKORY CREEK 113.0
END DESCRIPTION:
XS GIS Cut Line= 4
      2745601.99     10195360.27      2746849.43     10194499.67
      2747424.92     10194141.51      2748737.47      10194136.3
#Sta/Elev= 30
  3484.5 1276.62    4232 1264.89  4527.5  1262.9  4764.6 1265.03  4801.1 1253.58
  4843.9 1247.42  4922.6 1245.84  4951.4 1248.41  4955.9 1244.71  4957.4 1243.71
  5033.5 1244.71  5066.3 1246.49    5184 1251.15  5212.3 1253.97  5227.7 1258.57
  5285.5 1256.74    5328 1262.32  5489.7 1271.12  5547.5 1271.79  5858.6 1267.44
  6088.6 1246.11  6118.6 1245.38  6168.6 1247.46  6208.6 1258.28  6268.6 1258.62
  6288.6 1255.56    6539 1269.67  6668.6 1265.68  6808.6 1274.88  6990.4 1277.84
#Mann= 3 ,-1 , 0
  3484.5     .05       0  4764.6     .05       0  5066.3     .05       0
Bank Sta=4955.9,5033.5
XS Rating Curve= 0 ,0
Exp/Cntr=0.3,0.1

Type RM Length L Ch R = 1 ,56000   ,500,500,500
BEGIN DESCRIPTION:
HICKORY CREEK 112.0
END DESCRIPTION:
XS GIS Cut Line= 5
      2746091.61     10195693.57       2747123.3     10194896.21
      2747534.29     10194610.26      2748331.17     10194610.26
      2748616.25     10194377.01
#Sta/Elev= 30
  3696.1 1276.29  4019.6 1267.44  4177.2 1268.39  4276.8 1257.45  4320.3 1260.88
  4405.4 1254.21  4459.5 1261.44  4489.8 1261.65  4704.9  1263.7  4747.8 1260.69
  4775.5 1250.02  4821.9 1245.51  4967.8 1246.74  4972.8 1243.32  4974.3 1242.32
  5050.4 1243.32    5076 1248.41  5098.5  1248.5  5270.8 1252.71  5363.3 1264.52
  5460.8 1267.85  5592.1 1262.97  5772.1 1246.35  5852.1 1244.69  5872.1 1247.91
    5945 1249.32  6002.1 1249.76  6061.4 1258.65  6484.1 1272.13  6665.9  1272.9
#Mann= 11 ,-1 , 0
  3696.1     .05       0  4459.5     .12       0  4489.8     .05       0
  4704.9     .12       0  4821.9     .05       0  4972.8     .03       0
  5050.4     .05       0  5098.5     .12       0  5460.8     .05       0
    5945     .12       0  6061.4     .05       0
Bank Sta=4972.8,5050.4
XS Rating Curve= 0 ,0
Exp/Cntr=0.3,0.1

Type RM Length L Ch R = 1 ,55500   ,500,500,500
BEGIN DESCRIPTION:
HICKORY CREEK 111.0
END DESCRIPTION:
XS GIS Cut Line= 4
      2746820.72     10195881.13      2747328.99     10195342.34
      2747992.63     10195052.97      2748799.92      10194886.3
#Sta/Elev= 30
  4259.3 1281.47  4502.1 1266.02  4565.6 1267.62  4650.5 1259.19  4685.7 1260.69
  4714.1 1257.24  4749.7 1245.22  4763.9  1248.6  4813.2 1250.98  4914.7 1244.28
  4967.4  1242.2  4968.9  1241.2  5045.1  1242.2  5072.8 1247.31  5105.3 1245.03
  5116.4 1247.68  5181.1 1246.92  5238.8  1254.9  5337.9 1262.43  5378.2 1260.24
  5408.2 1247.65  5431.6 1243.54  5465.9 1242.85  5536.2 1247.14  5596.8 1257.62
  5809.6 1258.28  6033.4  1258.3  6370.4  1274.8  6443.7 1271.78  6548.3 1273.52
#Mann= 7 ,-1 , 0
  4259.3     .05       0  4763.9     .12       0  4914.7     .05       0
  4967.4     .05       0  5045.1     .05       0  5596.8     .12       0
  5809.6     .05       0
Bank Sta=4967.4,5045.1
XS Rating Curve= 0 ,0
Exp/Cntr=0.3,0.1