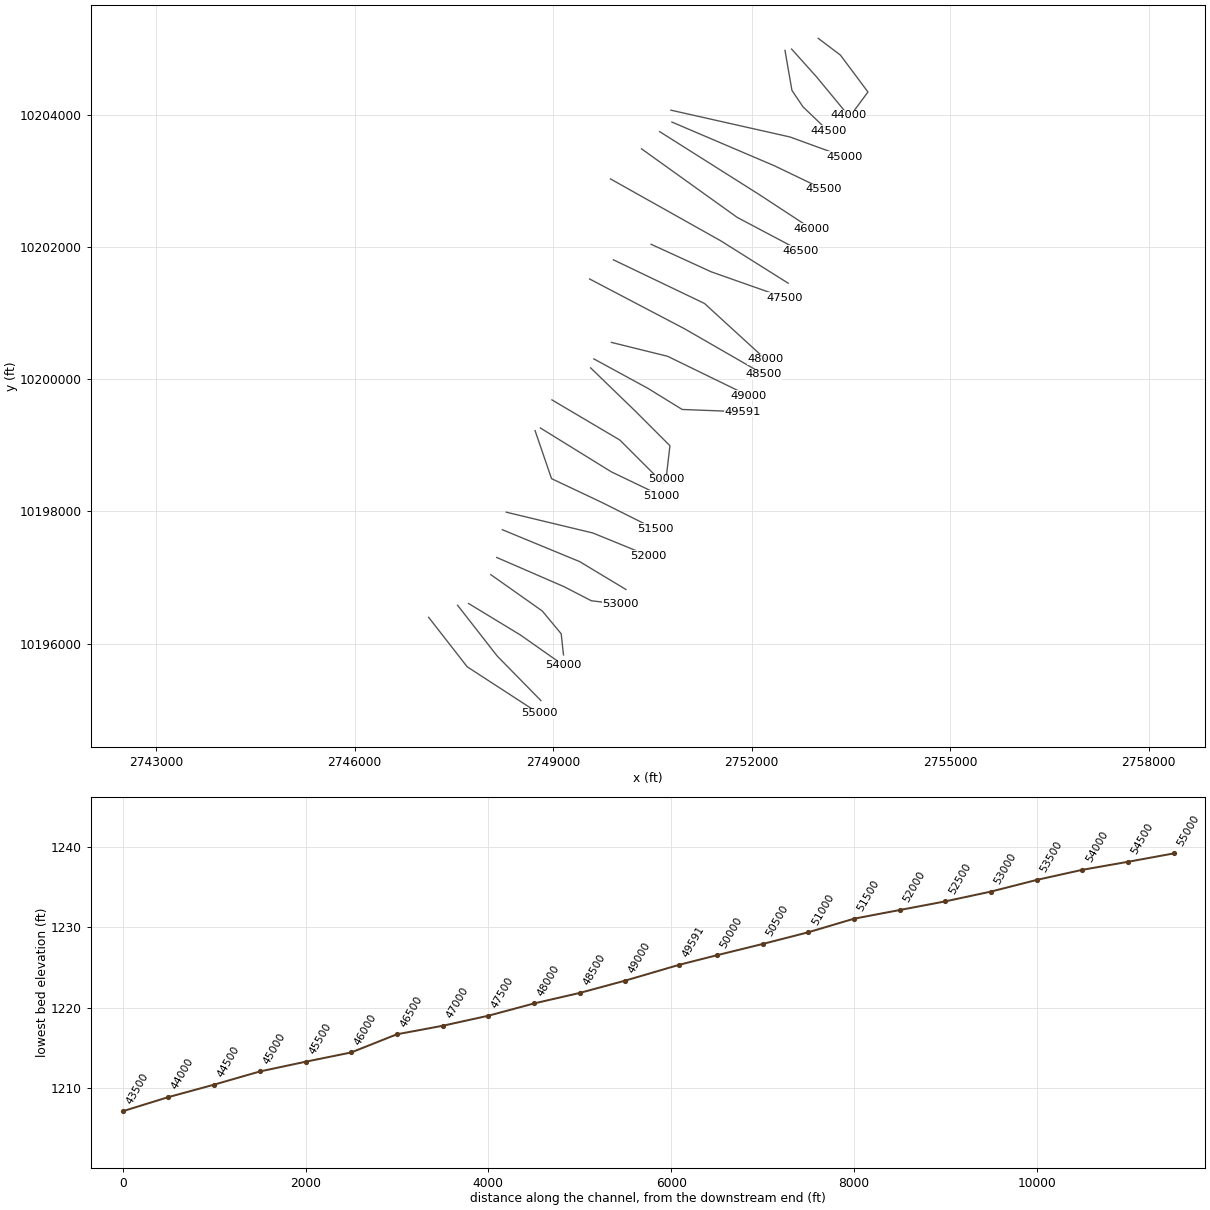
HEC-RAS study HICKORY CREEK.prj: HICKORY CREEK Base Level Engineering

--- HICKORY CREEK.g01 (geometry) --- (continued)

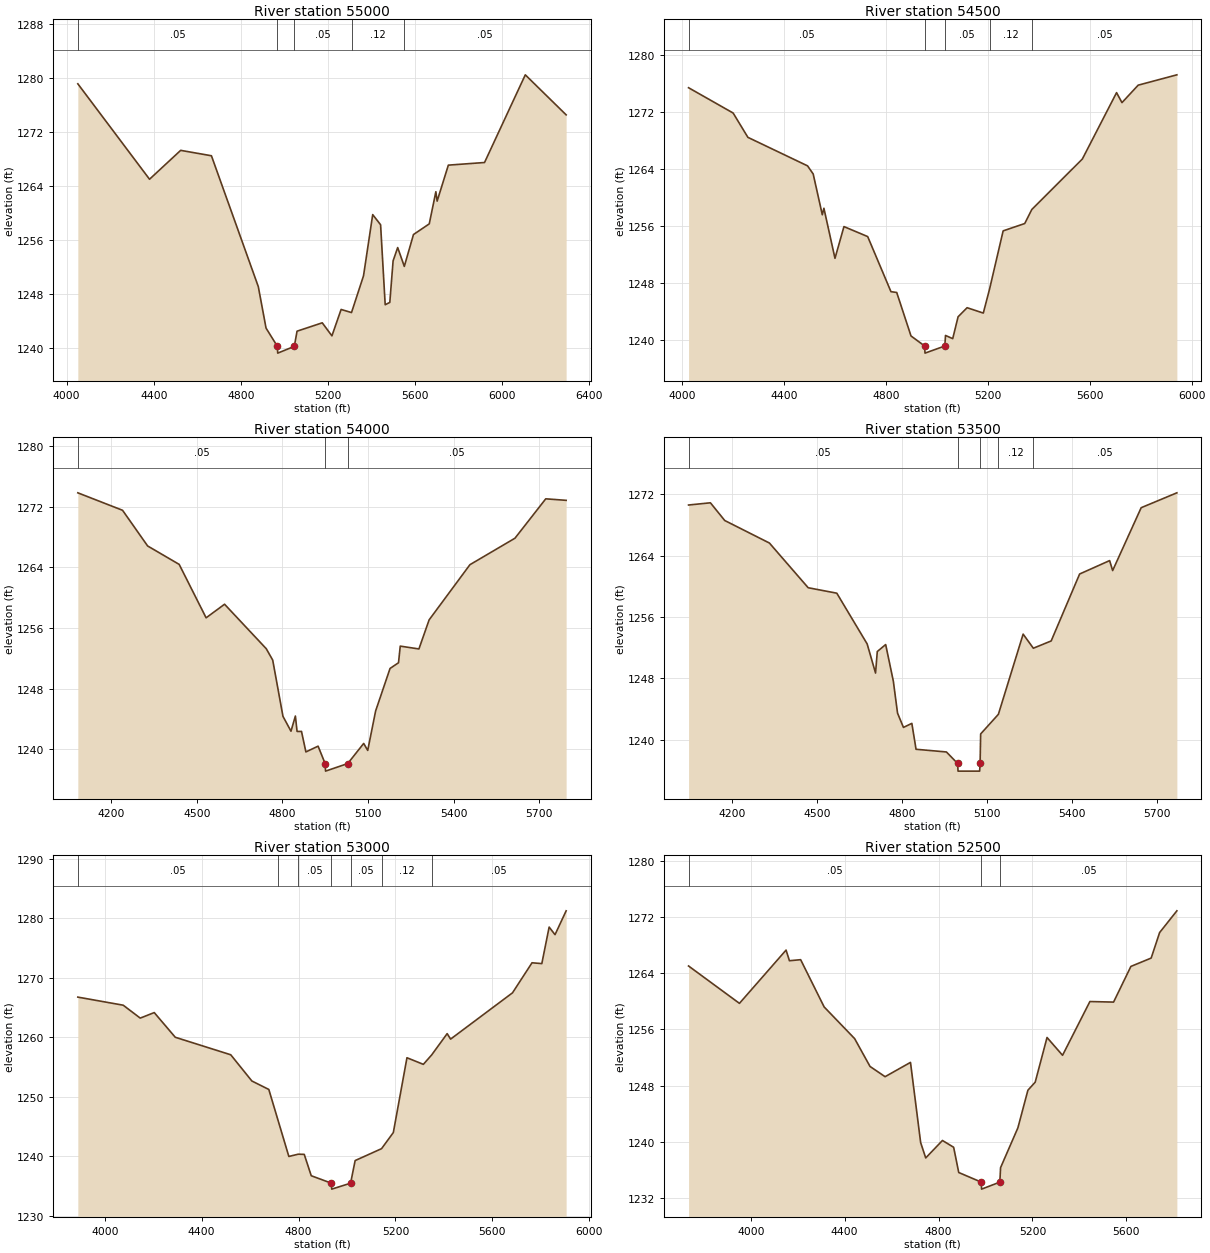
Type RM Length L Ch R = 1 ,55000   ,500,500,500
BEGIN DESCRIPTION:
HICKORY CREEK 110.0
END DESCRIPTION:
XS GIS Cut Line= 3
      2747117.63     10196396.72      2747700.26     10195648.39
      2748784.29      10194943.6
#Sta/Elev= 30
  4051.6 1279.09  4380.7 1264.95  4523.7 1269.23  4664.8 1268.43    4880 1249.04
  4915.5  1242.9  4967.6 1240.19  4969.1 1239.19  5045.3 1240.19  5057.8 1242.44
  5173.5 1243.68  5217.9 1241.75  5260.1 1245.66  5307.8  1245.2  5362.9 1250.64
  5405.1 1259.71  5441.3 1258.21  5462.4 1246.36  5483.6  1246.7  5498.7 1252.86
  5519.8 1254.83  5550.2 1252.04  5592.2 1256.76  5664.7 1258.34    5695  1263.1
  5700.9 1261.71  5752.3 1267.04  5918.4 1267.43  6105.5 1280.42    6293 1274.49
#Mann= 5 ,-1 , 0
  4051.6     .05       0  4967.6     .03       0  5045.3     .05       0
  5307.8     .12       0  5550.2     .05       0
Bank Sta=4967.6,5045.3
XS Rating Curve= 0 ,0
Exp/Cntr=0.3,0.1

Type RM Length L Ch R = 1 ,54500   ,500,500,500
BEGIN DESCRIPTION:
HICKORY CREEK 109.0
END DESCRIPTION:
XS GIS Cut Line= 3
      2747555.13       10196579.      2748155.16     10195809.87
      2748814.64     10195137.22
#Sta/Elev= 30
  4024.5 1275.38  4199.6 1271.83  4257.5 1268.42  4491.8 1264.42  4513.9 1263.28
  4549.7 1257.56    4556 1258.47  4599.5 1251.45  4634.7  1255.9  4727.9  1254.5
  4819.3 1246.77  4841.9 1246.66    4898 1240.56  4951.5 1239.15    4953 1238.15
  5030.8 1239.15  5033.5 1240.63  5061.8 1240.18  5082.9 1243.25  5118.3 1244.52
  5181.9 1243.77  5206.7 1247.17  5259.8  1255.3  5344.6 1256.33  5372.4  1258.3
  5570.8 1265.38  5705.2 1274.69  5726.4 1273.29  5790.1 1275.74    5942 1277.19
#Mann= 5 ,-1 , 0
  4024.5     .05       0  4951.5     .03       0  5030.8     .05       0
  5206.7     .12       0  5372.4     .05       0
Bank Sta=4951.5,5030.8
XS Rating Curve= 0 ,0
Exp/Cntr=0.3,0.1

Type RM Length L Ch R = 1 ,54000   ,500,500,500
BEGIN DESCRIPTION:
HICKORY CREEK 108.0
END DESCRIPTION:
XS GIS Cut Line= 3
      2747721.81     10196605.04       2748504.9     10196129.24
      2749154.08     10195672.77
#Sta/Elev= 30
  4083.7 1273.82  4240.3 1271.52  4328.1 1266.82  4438.6 1264.39  4532.9 1257.35
  4597.5 1259.14  4743.5 1253.28  4766.1 1251.78    4802 1244.37  4830.1 1242.41
  4845.5 1244.41  4851.4 1242.38  4866.9 1242.38  4882.3 1239.68    4925 1240.44
  4949.6 1238.15  4951.1 1237.15  5028.9 1238.15  5084.7  1240.8  5098.8 1239.88
  5126.5 1245.08    5177 1250.68  5206.6 1251.43  5212.7 1253.62  5278.1 1253.25
  5313.8 1257.08  5456.7 1264.35  5614.4 1267.84  5722.2 1273.03  5793.6 1272.83
#Mann= 3 ,-1 , 0
  4083.7     .05       0  4949.6     .03       0  5028.9     .05       0
Bank Sta=4949.6,5028.9
XS Rating Curve= 0 ,0
Exp/Cntr=0.3,0.1

Type RM Length L Ch R = 1 ,53500   ,500,500,500
BEGIN DESCRIPTION:
HICKORY CREEK 107.0
END DESCRIPTION:
XS GIS Cut Line= 4
      2748056.84     10197041.99      2748834.89     10196492.54
      2749121.04     10196147.66      2749156.01       10195828.
#Sta/Elev= 30
  4047.5  1270.6  4124.6 1270.89  4175.1 1268.58  4332.7 1265.64  4469.4 1259.81
  4570.3  1259.1  4677.4 1252.48    4707 1248.68  4713.1 1251.49  4742.7  1252.4
  4769.7 1247.63  4784.5 1243.46  4805.4 1241.59    4835 1242.12  4849.8 1238.74
  4956.9 1238.39  4996.4 1236.89  4997.9 1235.89  5074.2 1235.89  5075.7 1236.89
  5077.7 1240.74  5140.2  1243.3  5227.5 1253.76  5263.5 1251.92  5326.4 1252.87
  5426.7  1261.6  5532.5 1263.35  5543.2 1262.05  5643.8 1270.25  5769.7 1272.19
#Mann= 5 ,-1 , 0
  4047.5     .05       0  4996.4     .03       0  5075.7     .05       0
  5140.2     .12       0  5263.5     .05       0
Bank Sta=4996.4,5075.7
XS Rating Curve= 0 ,0
Exp/Cntr=0.3,0.1

Type RM Length L Ch R = 1 ,53000   ,500,500,500
BEGIN DESCRIPTION:
HICKORY CREEK 106.0
END DESCRIPTION:
XS GIS Cut Line= 4
      2748146.78     10197301.78      2749165.83     10196859.21
      2749575.69     10196647.28      2750015.36     10196592.32
#Sta/Elev= 30
    3889 1266.71  4076.3 1265.35  4146.6 1263.18  4204.4 1264.11  4291.2 1259.96
  4520.1 1257.02  4607.4 1252.61  4677.3 1251.19  4713.4 1246.27    4760 1239.93
  4798.4 1240.31  4823.5 1240.28  4852.4 1236.69  4935.5 1235.44    4937 1234.44
  5014.8 1235.44  5033.6 1239.24  5142.6 1241.24  5191.2 1243.95  5247.5 1256.52
  5315.1 1255.41  5349.2 1256.98  5413.4 1260.57  5427.6 1259.65  5683.1 1267.43
  5763.7 1272.48  5804.1 1272.34  5834.3 1278.48  5858.6  1277.2  5904.5 1281.21
#Mann= 7 ,-1 , 0
    3889     .05       0  4713.4     .12       0  4798.4     .05       0
  4935.5     .03       0  5014.8     .05       0  5142.6     .12       0
  5349.2     .05       0
Bank Sta=4935.5,5014.8
XS Rating Curve= 0 ,0
Exp/Cntr=0.3,0.1

Type RM Length L Ch R = 1 ,52500   ,500,500,500
BEGIN DESCRIPTION:
HICKORY CREEK 105.0
END DESCRIPTION:
XS GIS Cut Line= 3
      2748231.69     10197721.46      2749400.89     10197238.56
      2750099.48     10196817.63
#Sta/Elev= 30
    3735 1265.05  3951.8 1259.72  4150.5 1267.32  4164.8  1265.8  4212.6 1265.95
  4312.7 1259.21  4442.6 1254.69  4508.2 1250.72  4572.4 1249.26  4680.6  1251.3
  4723.9 1239.86  4745.5 1237.67  4816.8 1240.16  4864.5 1239.19  4886.2 1235.59
    4982 1234.22  4983.5 1233.22  5061.4 1234.22  5064.4 1236.28  5138.2 1241.96
  5180.9 1247.33    5212 1248.48  5262.4 1254.85  5328.5 1252.31    5445 1259.98
  5545.9  1259.9  5619.7 1264.99  5706.1 1266.18  5742.1 1269.82  5815.6 1272.92
#Mann= 3 ,-1 , 0
    3735     .05       0    4982     .03       0  5061.4     .05       0
Bank Sta=4982,5061.4
XS Rating Curve= 0 ,0
Exp/Cntr=0.3,0.1

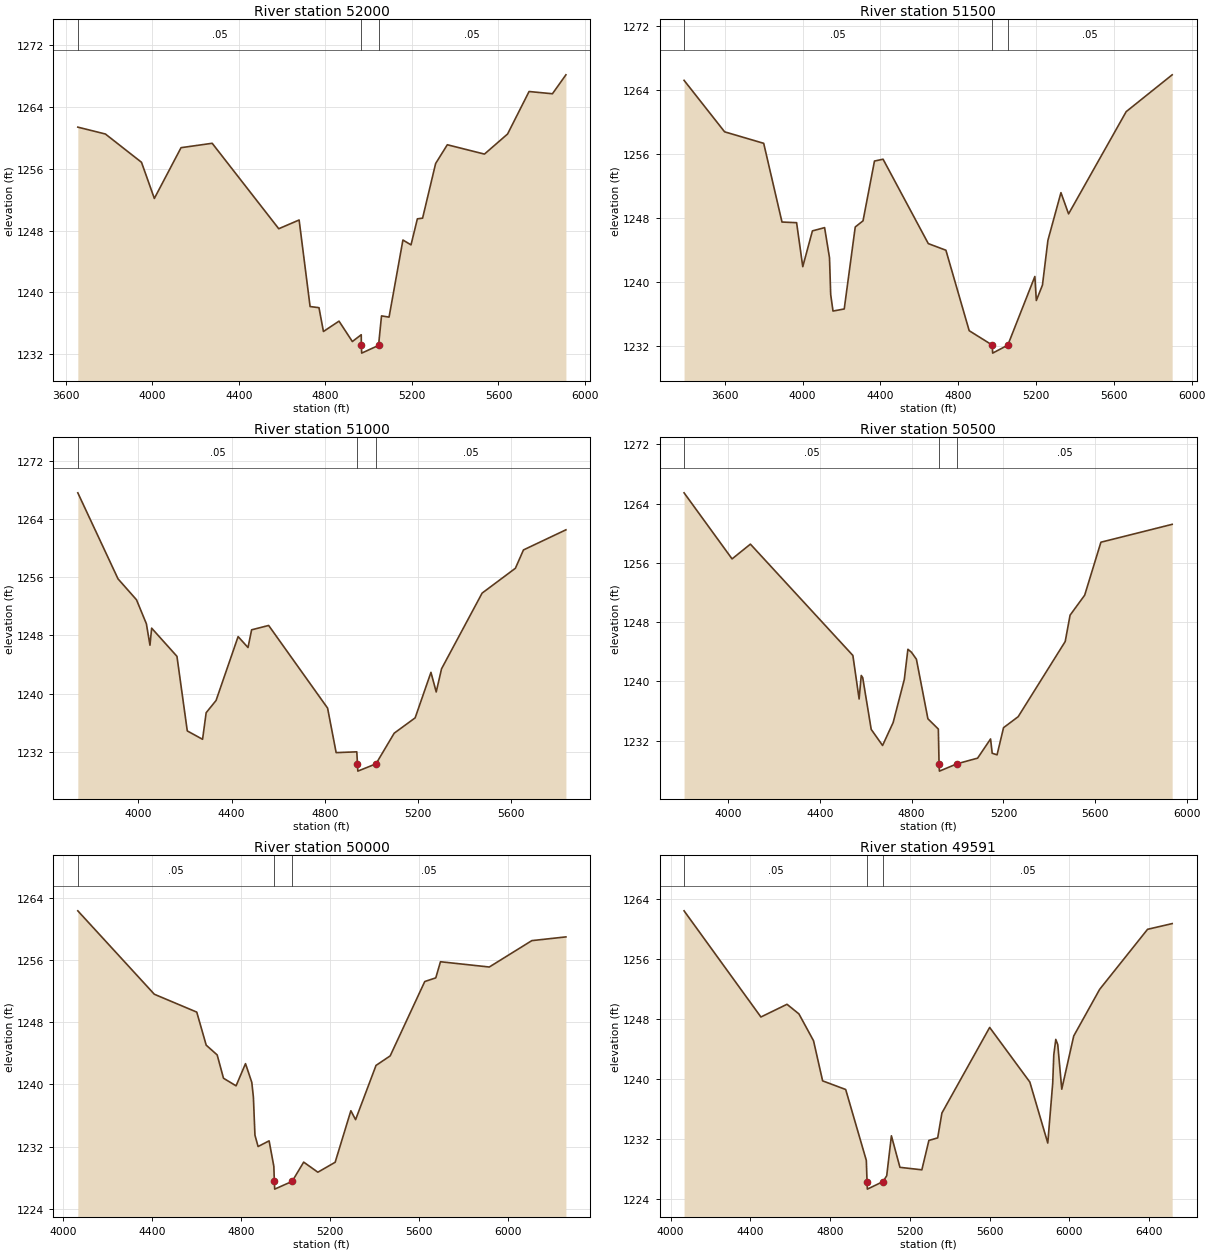
Type RM Length L Ch R = 1 ,52000   ,500,500,500
BEGIN DESCRIPTION:
HICKORY CREEK 104.0
END DESCRIPTION:
XS GIS Cut Line= 3
      2748291.68     10197986.25      2749599.02     10197671.94
      2750443.35     10197327.44
#Sta/Elev= 30
  3655.4 1261.39  3782.9  1260.5  3949.8 1256.84  4009.2 1252.16  4132.6 1258.73
  4276.6  1259.3  4584.3 1248.24  4678.5 1249.37  4729.2 1238.17  4770.3 1238.02
  4790.9 1234.94  4862.9 1236.28  4924.6 1233.64  4965.7 1234.52  4966.3 1233.14
  4967.8 1232.14  5045.7 1233.14  5059.4 1236.96  5094.3  1236.8  5158.4 1246.78
  5195.8 1246.15  5225.2 1249.52  5249.3 1249.61  5309.6 1256.68  5363.6 1259.11
  5535.3  1257.9  5642.2  1260.5  5741.6    1266  5849.6 1265.71  5911.9 1268.16
#Mann= 3 ,-1 , 0
  3655.4     .05       0  4966.3     .05       0  5045.7     .05       0
Bank Sta=4966.3,5045.7
XS Rating Curve= 0 ,0
Exp/Cntr=0.3,0.1

Type RM Length L Ch R = 1 ,51500   ,500,500,500
BEGIN DESCRIPTION:
HICKORY CREEK 103.0
END DESCRIPTION:
XS GIS Cut Line= 4
      2748726.34     10199220.31        2748975.       10198494.
      2749735.31     10198134.08      2750539.99     10197731.42
#Sta/Elev= 30
  3391.1 1265.23  3599.5 1258.78  3800.4 1257.34  3894.4 1247.48  3969.5  1247.4
  4001.2 1241.89  4050.8 1246.37  4113.4 1246.78  4138.6 1243.01  4144.7  1238.4
  4156.6 1236.33  4214.3 1236.59  4270.9 1246.86  4310.9 1247.63  4369.8 1255.12
    4414 1255.35  4646.4 1244.78  4736.9 1243.95  4856.6 1233.87  4975.6 1232.06
  4977.1 1231.06    5055 1232.06  5194.1 1240.66  5201.7 1237.65  5233.2 1239.59
  5261.2 1245.19  5328.2 1251.16  5367.4  1248.5  5663.6 1261.31  5899.8 1265.92
#Mann= 3 ,-1 , 0
  3391.1     .05       0  4975.6     .03       0    5055     .05       0
Bank Sta=4975.6,5055
XS Rating Curve= 0 ,0
Exp/Cntr=0.3,0.1

Type RM Length L Ch R = 1 ,51000   ,500,500,500
BEGIN DESCRIPTION:
HICKORY CREEK 102.0
END DESCRIPTION:
XS GIS Cut Line= 3
      2748806.26     10199260.27      2749877.53     10198597.34
      2750629.88     10198236.05
#Sta/Elev= 30
  3740.2 1267.58  3912.7 1255.77  3991.9  1252.9  4034.4  1249.6  4049.8 1246.66
    4057    1249  4165.6 1245.13  4209.9 1234.89  4275.5 1233.74  4290.9 1237.39
  4333.4 1239.07    4428 1247.84  4470.5 1246.34  4485.9 1248.77  4559.1 1249.37
    4812 1238.02  4848.7 1231.91  4937.3 1232.02  4940.2 1230.37  4941.7 1229.37
  5019.6 1230.37  5097.8 1234.58  5187.6 1236.68  5255.5 1242.93  5278.1 1240.24
  5300.8 1243.41    5475 1253.81  5617.8 1257.22  5652.5 1259.74  5834.6  1262.5
#Mann= 3 ,-1 , 0
  3740.2     .05       0  4940.2     .03       0  5019.6     .05       0
Bank Sta=4940.2,5019.6
XS Rating Curve= 0 ,0
Exp/Cntr=0.3,0.1

Type RM Length L Ch R = 1 ,50500   ,500,500,500
BEGIN DESCRIPTION:
HICKORY CREEK 101.0
END DESCRIPTION:
XS GIS Cut Line= 3
      2748981.16     10199684.93      2750006.74     10199078.02
      2750668.74     10198417.02
#Sta/Elev= 30
  3808.3 1265.44  4017.5 1256.53  4097.4 1258.52    4544 1243.51  4571.2 1237.64
  4580.5 1240.81  4586.9 1240.52  4623.9 1233.54  4673.4 1231.37  4719.5 1234.46
  4768.2 1240.28  4783.8 1244.34  4799.4 1243.94  4820.9    1243    4871 1234.97
  4916.5 1233.58  4919.6 1228.91  4921.1 1227.91    4999 1228.91  5087.6 1229.66
  5144.1 1232.25  5151.2 1230.32  5172.4 1230.11  5200.7 1233.77  5264.4 1235.25
  5469.4 1245.39  5490.6 1248.94  5554.3 1251.64    5625 1258.78  5935.5 1261.19
#Mann= 3 ,-1 , 0
  3808.3     .05       0  4919.6     .03       0    4999     .05       0
Bank Sta=4919.6,4999
XS Rating Curve= 0 ,0
Exp/Cntr=0.3,0.1

Type RM Length L Ch R = 1 ,50000   ,409,409,409
BEGIN DESCRIPTION:
HICKORY CREEK 100.0
END DESCRIPTION:
XS GIS Cut Line= 4
      2749565.68     10200169.57      2750236.86     10199519.47
       2750764.7     10198991.61      2750704.82      10198480.9
#Sta/Elev= 30
  4065.6 1262.37  4409.7 1251.62  4600.5 1249.32    4643 1245.06  4692.4  1243.8
  4720.7  1240.8  4777.3 1239.82  4819.7 1242.68    4848 1240.27  4855.2 1238.38
  4862.2 1233.47  4876.3    1232  4925.9 1232.73  4947.1 1229.45  4949.5 1227.51
    4951 1226.51  5029.5 1227.51  5081.4 1229.99  5145.1 1228.69  5222.9 1229.97
  5293.6 1236.61  5314.8 1235.46  5406.7 1242.45  5470.4 1243.68  5625.9 1253.26
  5675.4 1253.73  5696.6 1255.81  5916.1 1255.13  6107.4 1258.53  6260.7 1259.01
#Mann= 3 ,-1 , 0
  4065.6     .05       0  4949.5     .03       0  5029.5     .05       0
Bank Sta=4949.5,5029.5
XS Rating Curve= 0 ,0
Exp/Cntr=0.3,0.1

Type RM Length L Ch R = 1 ,49591   ,591,591,591
BEGIN DESCRIPTION:
HICKORY CREEK 99.0
END DESCRIPTION:
XS GIS Cut Line= 4
      2749615.66     10200304.45        2750434.       10199858.
      2750949.63     10199540.04      2751858.98     10199505.07
#Sta/Elev= 30
  4067.8 1262.37  4453.2 1248.24  4584.1 1249.93  4643.9 1248.65  4717.1 1245.08
  4762.7 1239.74  4878.4 1238.59  4981.9 1229.15  4985.5 1226.33    4987 1225.33
  5065.5 1226.33  5084.2 1227.11  5107.7 1232.43  5150.5 1228.23  5260.4  1227.9
  5295.7 1231.81  5339.8 1232.15    5361 1235.46  5600.5 1246.85    5802 1239.58
    5892 1231.46  5916.7 1239.44  5922.1 1243.19  5932.1 1245.26  5942.1 1244.56
  5962.1 1238.63  6022.1 1245.71  6152.2 1251.92  6392.4 1259.91  6515.8 1260.67
#Mann= 3 ,-1 , 0
  4067.8     .05       0  4985.5     .03       0  5065.5     .05       0
Bank Sta=4985.5,5065.5
XS Rating Curve= 0 ,0
Exp/Cntr=0.3,0.1

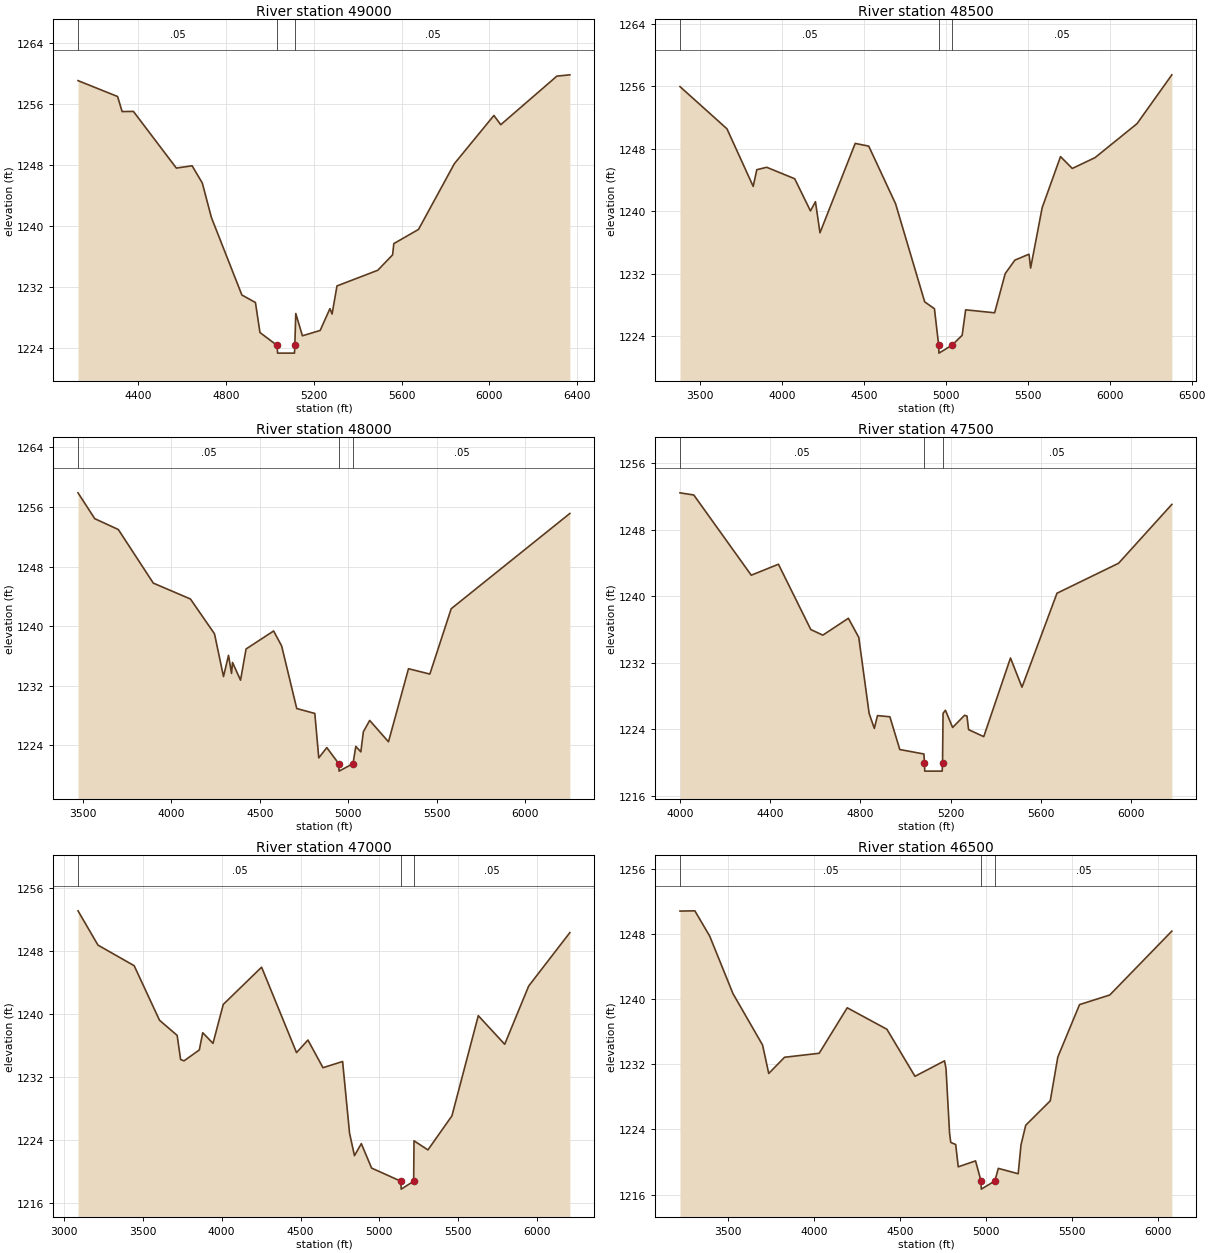
Type RM Length L Ch R = 1 ,49000   ,500,500,500
BEGIN DESCRIPTION:
HICKORY CREEK 98.0
END DESCRIPTION:
XS GIS Cut Line= 3
      2749880.48     10200554.26      2750729.75     10200344.05
      2751958.88     10199744.87
#Sta/Elev= 30
  4125.1 1259.04  4305.6 1256.96  4326.2 1254.99  4377.7 1255.01  4573.4 1247.59
  4645.3 1247.89  4691.8 1245.63  4733.2 1241.12  4872.2 1230.97    4934 1229.99
  4954.6 1226.06  5033.2 1224.36  5034.7 1223.36    5112 1223.36  5113.5 1224.36
  5117.9 1228.55  5148.1 1225.63  5229.1 1226.33  5273.6 1229.19  5283.3 1228.48
  5305.8 1232.16  5491.7 1234.21  5559.3 1236.23  5564.8  1237.7  5677.5 1239.56
    5841 1248.17  6021.1 1254.48  6052.3 1253.27  6308.2 1259.63  6367.4  1259.8
#Mann= 3 ,-1 , 0
  4125.1     .05       0  5033.2     .05       0  5113.5     .05       0
Bank Sta=5033.2,5113.5
XS Rating Curve= 0 ,0
Exp/Cntr=0.3,0.1

Type RM Length L Ch R = 1 ,48500   ,500,500,500
BEGIN DESCRIPTION:
HICKORY CREEK 97.0
END DESCRIPTION:
XS GIS Cut Line= 3
      2749550.73     10201513.51      2750987.35     10200759.22
      2752182.17      10200070.5
#Sta/Elev= 30
  3377.4 1255.98  3664.2 1250.57  3824.2 1243.19  3846.2 1245.33  3906.7 1245.64
  4077.5 1244.17  4173.6 1240.05  4204.1 1241.23  4231.8 1237.25  4446.7  1248.7
  4529.3 1248.35  4693.2 1240.96  4870.8 1228.39  4930.3 1227.51  4956.1 1222.82
  4957.6 1221.82  5036.4 1222.82  5099.3  1224.1  5120.8 1227.37  5297.5 1226.99
  5362.2 1232.01    5421 1233.74  5507.3  1234.5  5517.3 1232.73  5587.7 1240.46
  5699.7 1247.01  5771.4 1245.49  5909.9 1246.87  6166.6 1251.23  6379.1 1257.49
#Mann= 3 ,-1 , 0
  3377.4     .05       0  4956.1     .03       0  5036.4     .05       0
Bank Sta=4956.1,5036.4
XS Rating Curve= 0 ,0
Exp/Cntr=0.3,0.1

Type RM Length L Ch R = 1 ,48000   ,500,500,500
BEGIN DESCRIPTION:
HICKORY CREEK 96.0
END DESCRIPTION:
XS GIS Cut Line= 3
      2749910.44     10201803.29       2751286.2     10201143.71
      2752208.68     10200299.44
#Sta/Elev= 30
  3474.3  1257.9  3568.8 1254.43  3701.9 1252.97  3899.3 1245.77  4108.8 1243.64
  4244.7 1238.96  4295.5 1233.22  4323.8 1236.06  4340.9 1233.64  4346.4 1235.11
  4391.7 1232.73  4422.8 1236.92  4578.5 1239.34  4623.8 1237.32  4708.9 1228.92
  4810.9 1228.26  4833.3 1222.29  4878.6 1223.67  4946.2 1221.51  4947.7 1220.51
  5026.5 1221.51  5042.3 1223.83  5070.7  1223.1  5084.9  1225.8  5120.7 1227.32
  5226.7 1224.45  5339.6 1234.27  5460.2 1233.55  5580.7 1242.33  6250.5 1255.13
#Mann= 3 ,-1 , 0
  3474.3     .05       0  4946.2     .03       0  5026.5     .05       0
Bank Sta=4946.2,5026.5
XS Rating Curve= 0 ,0
Exp/Cntr=0.3,0.1

Type RM Length L Ch R = 1 ,47500   ,500,500,500
BEGIN DESCRIPTION:
HICKORY CREEK 95.0
END DESCRIPTION:
XS GIS Cut Line= 3
      2750480.01     10202038.11      2751388.27     10201621.84
      2752502.09     10201229.21
#Sta/Elev= 30
  4000.9 1252.46  4062.1  1252.2  4316.8 1242.55  4437.3 1243.87  4580.8 1236.01
  4634.1 1235.34  4747.3 1237.37  4793.3 1235.07  4839.3 1225.92  4862.3 1224.12
  4876.2 1225.66  4931.2 1225.52  4975.2 1221.58  5082.1 1221.04  5084.3 1219.98
  5085.8 1218.98  5163.1 1218.98  5164.6 1219.98  5166.9 1225.94  5177.5  1226.3
  5209.3 1224.23  5262.3  1225.7  5272.9 1225.61  5280.1 1223.97  5347.3 1223.13
  5465.8 1232.59  5516.8 1229.08  5671.8 1240.38    5945 1243.99    6181 1251.07
#Mann= 3 ,-1 , 0
  4000.9     .05       0  5084.3     .03       0  5164.6     .05       0
Bank Sta=5084.3,5164.6
XS Rating Curve= 0 ,0
Exp/Cntr=0.3,0.1

Type RM Length L Ch R = 1 ,47000   ,500,500,500
BEGIN DESCRIPTION:
HICKORY CREEK 94.0
END DESCRIPTION:
XS GIS Cut Line= 3
      2749865.49     10203027.34      2751530.54     10202091.95
      2752552.06     10201449.41
#Sta/Elev= 30
  3090.2 1253.14  3216.7 1248.78    3446 1246.16  3606.6 1239.22  3718.5 1237.29
  3740.2 1234.23  3761.9 1234.05  3858.8 1235.44  3880.5 1237.63  3945.5 1236.28
  4010.6 1241.23  4253.5 1245.97  4474.8  1235.1  4547.1  1236.7  4642.5 1233.18
  4766.8 1233.97  4810.9 1224.83    4842 1221.99  4885.4 1223.52  4950.4 1220.41
  5136.6 1218.73  5138.1 1217.73    5217 1218.73  5219.2 1223.88  5307.5 1222.72
  5459.4 1227.05  5626.6  1239.8  5793.9 1236.16  5945.8 1243.57  6206.8 1250.37
#Mann= 3 ,-1 , 0
  3090.2     .05       0  5136.6     .03       0    5217     .05       0
Bank Sta=5136.6,5217
XS Rating Curve= 0 ,0
Exp/Cntr=0.3,0.1

Type RM Length L Ch R = 1 ,46500   ,500,500,500
BEGIN DESCRIPTION:
HICKORY CREEK 93.0
END DESCRIPTION:
XS GIS Cut Line= 3
      2750335.07     10203482.03      2751780.79     10202445.18
      2752738.25     10201938.19
#Sta/Elev= 30
  3220.9 1250.83  3307.5 1250.86  3393.5 1247.77  3529.3 1240.69  3701.6 1234.37
  3737.4 1230.88  3829.5 1232.87  4030.9 1233.36  4194.2 1238.95  4425.1 1236.31
  4588.5 1230.53  4760.4 1232.43    4769  1231.5  4789.9  1223.5  4796.8 1222.41
  4825.5 1222.15  4840.2 1219.41  4940.9 1220.14  4972.9 1217.67  4974.4 1216.67
  5053.3 1217.67  5073.4 1219.22  5189.1 1218.56  5205.5  1222.1  5233.1 1224.52
  5375.8 1227.52  5419.8  1232.9  5546.2 1239.34  5722.2 1240.52  6083.4 1248.37
#Mann= 3 ,-1 , 0
  3220.9     .05       0  4972.9     .05       0  5053.3     .05       0
Bank Sta=4972.9,5053.3
XS Rating Curve= 0 ,0
Exp/Cntr=0.3,0.1

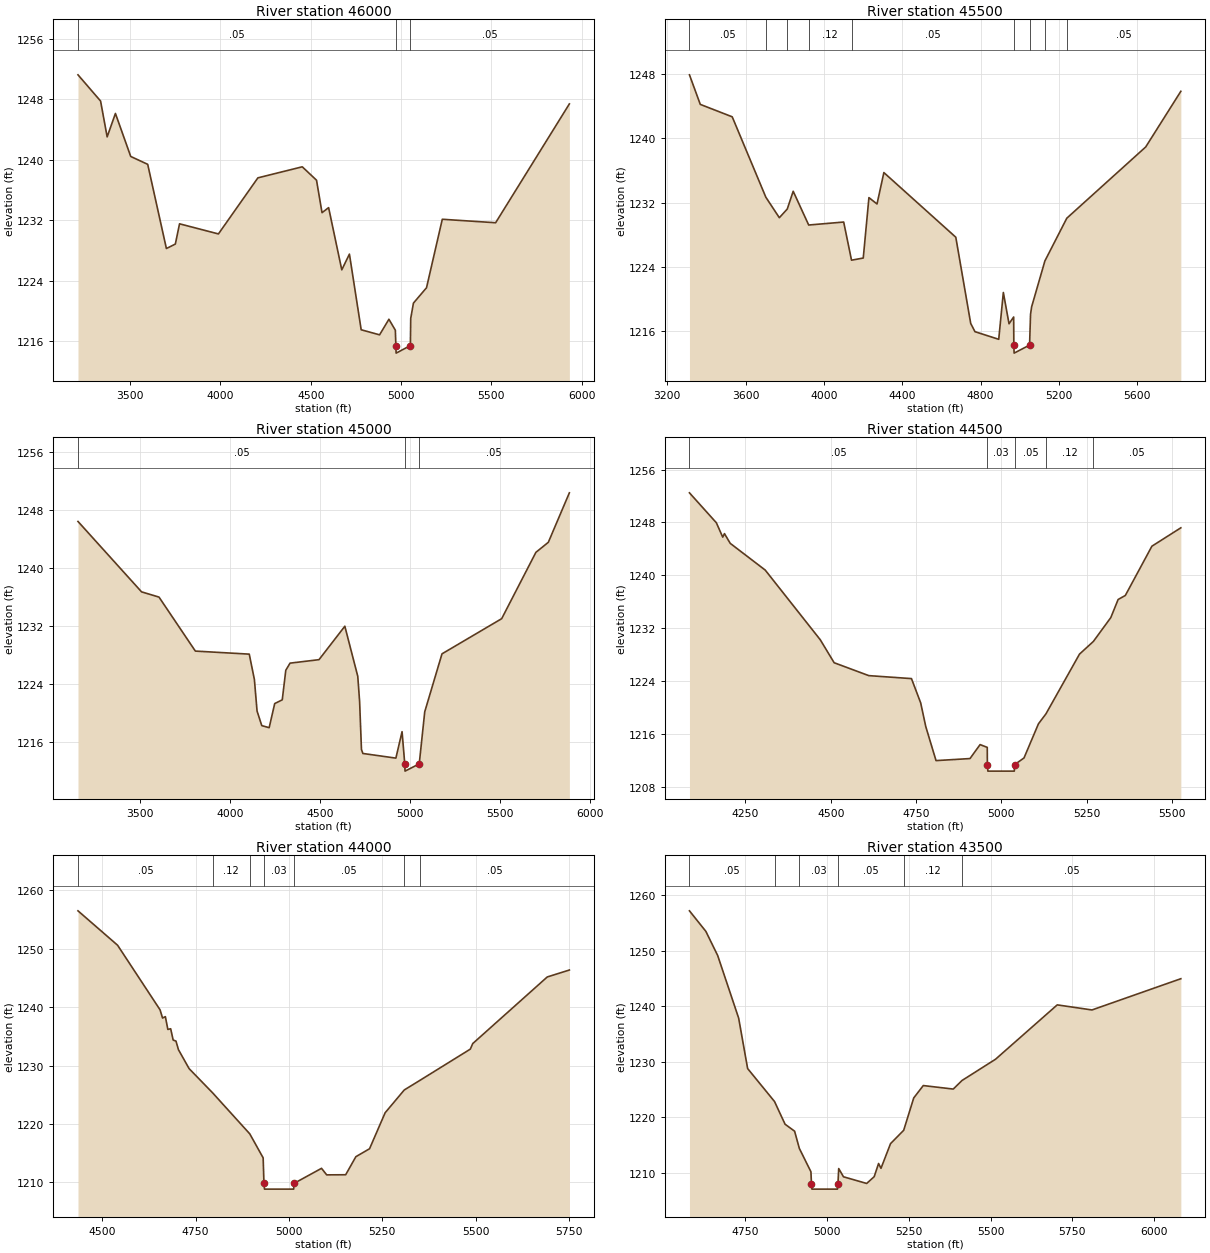
Type RM Length L Ch R = 1 ,46000   ,500,500,500
BEGIN DESCRIPTION:
HICKORY CREEK 92.0
END DESCRIPTION:
XS GIS Cut Line= 3
      2750609.91     10203741.79      2752122.11     10202785.32
      2752901.88     10202273.75
#Sta/Elev= 30
  3210.7 1251.23  3335.9 1247.76  3372.3 1243.02  3418.1 1246.12  3502.8 1240.43
  3596.9 1239.39  3700.4 1228.25    3750 1228.84  3773.3 1231.52  3988.6 1230.18
  4207.3  1237.6  4453.1 1239.06    4532 1237.29  4562.5 1232.99    4599 1233.66
  4671.9 1225.43  4714.3 1227.51  4779.4  1217.5  4881.3 1216.83    4933 1218.89
  4968.7 1217.44  4971.5 1215.41    4973 1214.41  5051.9 1215.41  5053.8    1219
  5068.9 1221.03  5141.3 1223.06  5228.7 1232.12  5524.1 1231.66  5932.6 1247.38
#Mann= 3 ,-1 , 0
  3210.7     .05       0  4971.5     .03       0  5051.9     .05       0
Bank Sta=4971.5,5051.9
XS Rating Curve= 0 ,0
Exp/Cntr=0.3,0.1

Type RM Length L Ch R = 1 ,45500   ,500,500,500
BEGIN DESCRIPTION:
HICKORY CREEK 91.0
END DESCRIPTION:
XS GIS Cut Line= 3
      2750794.78     10203886.68      2752346.06     10203224.49
       2753087.3      10202867.8
#Sta/Elev= 30
  3313.3  1247.9  3368.6 1244.22  3531.7 1242.67  3703.4 1232.66  3772.3 1230.11
  3812.8 1231.19  3843.1  1233.4  3922.2  1229.2  4100.9 1229.57  4140.9 1224.82
  4200.8 1225.09  4229.8 1232.61  4271.1 1231.82  4306.1 1235.73  4673.4 1227.68
  4749.5 1216.95  4771.3 1215.92  4892.6 1214.97  4916.2  1220.8  4945.2  1216.9
  4968.9 1217.75  4969.7 1214.25  4971.2 1213.25  5050.1 1214.25  5055.1 1218.08
  5060.7 1219.02  5128.4 1224.73  5240.3 1230.05  5643.2 1238.92  5822.6 1245.85
#Mann= 9 ,-1 , 0
  3313.3     .05       0  3703.4     .12       0  3812.8     .05       0
  3922.2     .12       0  4140.9     .05       0  4969.7     .03       0
  5050.1     .05       0  5128.4     .12       0  5240.3     .05       0
Bank Sta=4969.7,5050.1
XS Rating Curve= 0 ,0
Exp/Cntr=0.3,0.1

Type RM Length L Ch R = 1 ,45000   ,500,500,500
BEGIN DESCRIPTION:
HICKORY CREEK 90.0
END DESCRIPTION:
XS GIS Cut Line= 3
      2750779.72     10204066.56      2752579.61     10203661.04
      2753410.35     10203357.97
#Sta/Elev= 30
    3155  1246.4  3508.2 1236.71    3605 1235.99  3806.9 1228.56  4106.3 1228.14
  4134.9 1224.64  4149.6 1220.31  4175.9  1218.3  4216.9 1218.02  4247.7 1221.34
  4289.6 1221.85  4309.2 1225.92  4332.8  1226.9  4493.7 1227.38  4637.2 1231.98
    4709 1225.09  4719.2 1221.64  4729.5 1215.02  4737.5 1214.47  4920.7 1213.83
    4955 1217.47    4970 1213.04  4971.5 1212.04  5050.4 1213.04    5081 1220.21
  5176.8 1228.18  5508.3 1233.02  5698.4 1242.15  5767.4 1243.53  5884.3 1250.34
#Mann= 3 ,-1 , 0
    3155     .05       0    4970     .03       0  5050.4     .05       0
Bank Sta=4970,5050.4
XS Rating Curve= 0 ,0
Exp/Cntr=0.3,0.1

Type RM Length L Ch R = 1 ,44500   ,500,500,500
BEGIN DESCRIPTION:
HICKORY CREEK 89.0
END DESCRIPTION:
XS GIS Cut Line= 4
      2752503.43     10204970.86      2752608.35     10204366.32
      2752775.61     10204116.89      2753155.68     10203753.12
#Sta/Elev= 30
  4086.1 1252.48    4165 1247.95  4183.6 1245.78  4188.7 1246.31  4205.6 1244.84
  4308.1  1240.8  4469.5 1230.26  4510.1 1226.79  4611.6 1224.84  4736.7 1224.39
  4763.7 1220.72  4778.7 1217.12  4808.7 1211.99  4908.2  1212.3  4937.8 1214.41
  4958.8 1213.99  4959.1  1211.4  4960.6  1210.4    5038  1210.4  5039.5  1211.4
  5066.5 1212.39  5108.9 1217.56  5130.8 1219.06  5229.1 1228.09  5269.8 1230.01
  5320.9 1233.62  5342.3 1236.35  5363.4 1236.96  5441.3 1244.41  5526.1 1247.19
#Mann= 5 ,-1 , 0
  4086.1     .05       0  4959.1     .03       0  5039.5     .05       0
  5130.8     .12       0  5269.8     .05       0
Bank Sta=4959.1,5039.5
XS Rating Curve= 0 ,0
Exp/Cntr=0.3,0.1

Type RM Length L Ch R = 1 ,44000   ,500,500,500
BEGIN DESCRIPTION:
HICKORY CREEK 88.0
END DESCRIPTION:
XS GIS Cut Line= 3
      2752603.37     10204990.81      2752980.03     10204570.35
      2753457.69     10203991.61
#Sta/Elev= 30
  4435.5 1256.48  4541.5 1250.59  4655.1 1239.54  4661.8 1238.13  4669.3 1238.37
    4676 1236.18  4683.5  1236.3  4690.2 1234.36  4697.7 1234.19  4704.4 1232.71
  4732.9 1229.47  4795.9 1225.32  4895.3  1218.3    4931  1214.2  4933.1 1209.85
  4934.6 1208.85  5012.6 1208.85  5014.1 1209.85  5087.2 1212.41    5101 1211.29
  5151.8 1211.31  5179.1  1214.4  5215.7 1215.76  5257.3 1221.91  5308.6 1225.82
  5349.4 1227.42  5485.3 1232.81  5491.8 1233.76  5691.2 1245.16  5750.4 1246.35
#Mann= 7 ,-1 , 0
  4435.5     .05       0  4795.9     .12       0  4895.3     .05       0
  4933.1     .03       0  5014.1     .05       0  5308.6     .12       0
  5349.4     .05       0
Bank Sta=4933.1,5014.1
XS Rating Curve= 0 ,0
Exp/Cntr=0.3,0.1

Type RM Length L Ch R = 1 ,43500   ,500,500,500
BEGIN DESCRIPTION:
HICKORY CREEK 87.0
END DESCRIPTION:
XS GIS Cut Line= 4
      2753005.72     10205153.09      2753341.59     10204899.26
      2753757.46     10204341.34      2753527.62     10204031.55
#Sta/Elev= 30
    4579 1257.18  4629.1 1253.49  4665.3 1249.14  4729.4 1237.88  4756.9 1228.79
  4839.1 1222.86  4871.4 1218.77  4900.5 1217.52    4915 1214.42  4950.4 1210.22
  4952.1 1208.09  4953.6 1207.09  5031.6 1207.09  5033.1 1208.09  5035.4 1210.79
    5050 1209.31  5120.9 1208.11  5143.9 1209.33  5157.3  1211.7  5164.7 1210.84
  5193.9 1215.28  5234.1 1217.68  5264.8  1223.5    5294 1225.73  5385.7  1225.1
  5412.4 1226.64    5515 1230.47  5703.6 1240.25  5809.9 1239.34  6081.6 1244.96
#Mann= 6 ,-1 , 0
    4579     .05       0  4839.1     .12       0    4915     .03       0
  5033.1     .05       0  5234.1     .12       0  5412.4     .05       0
Bank Sta=4952.1,5033.1
XS Rating Curve= 0 ,0
Exp/Cntr=0.3,0.1