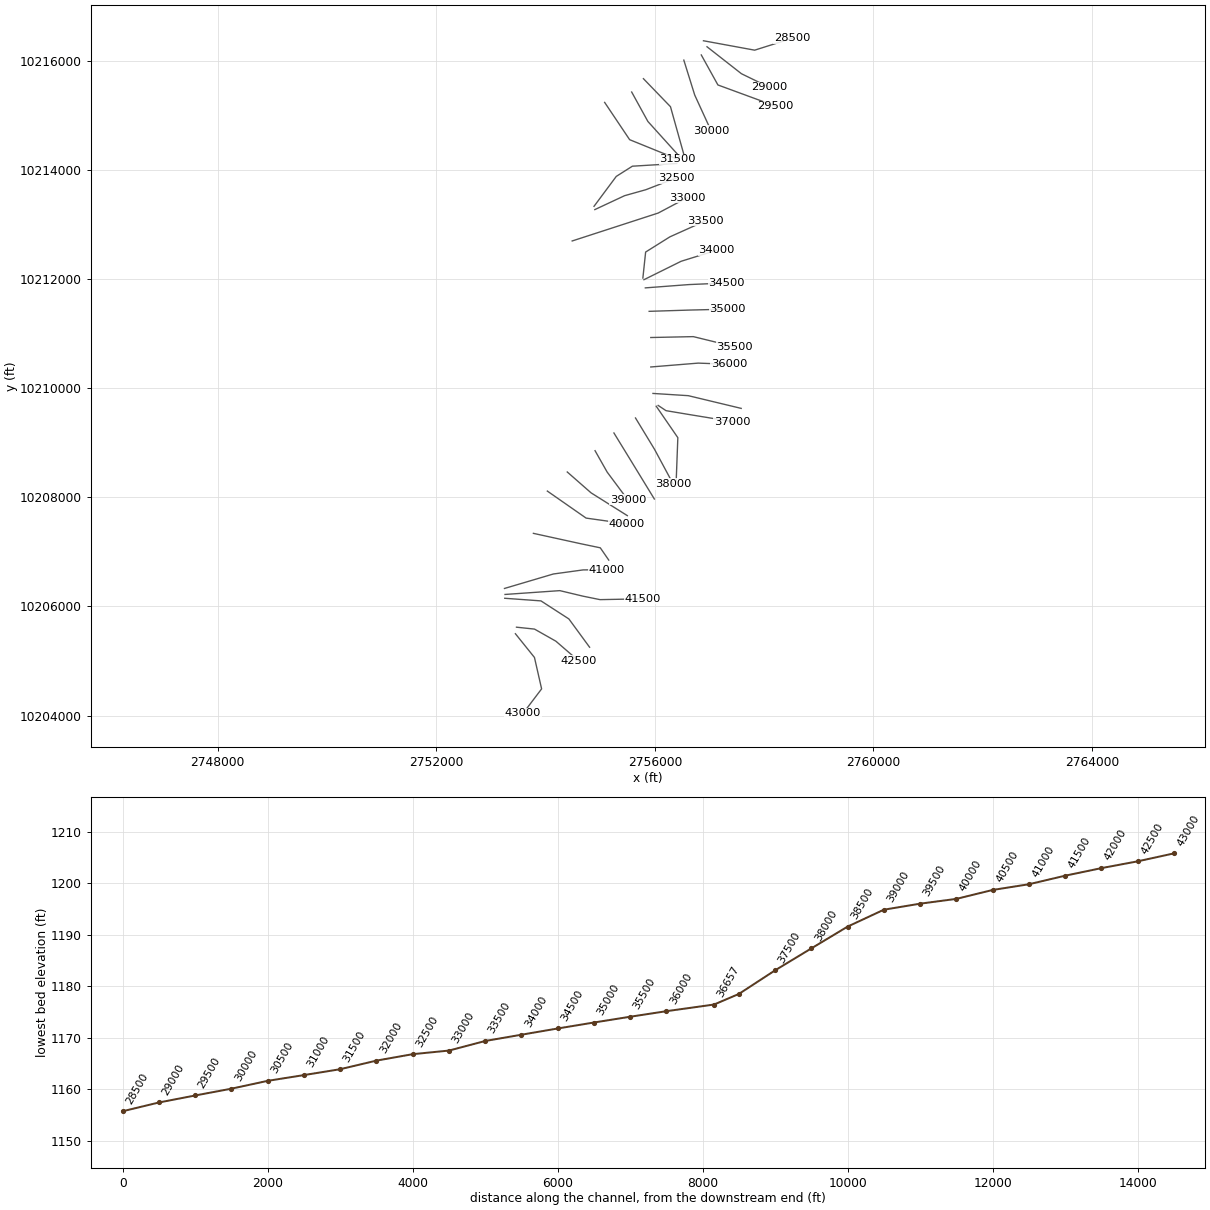
HEC-RAS study HICKORY CREEK.prj: HICKORY CREEK Base Level Engineering

--- HICKORY CREEK.g01 (geometry) --- (continued)

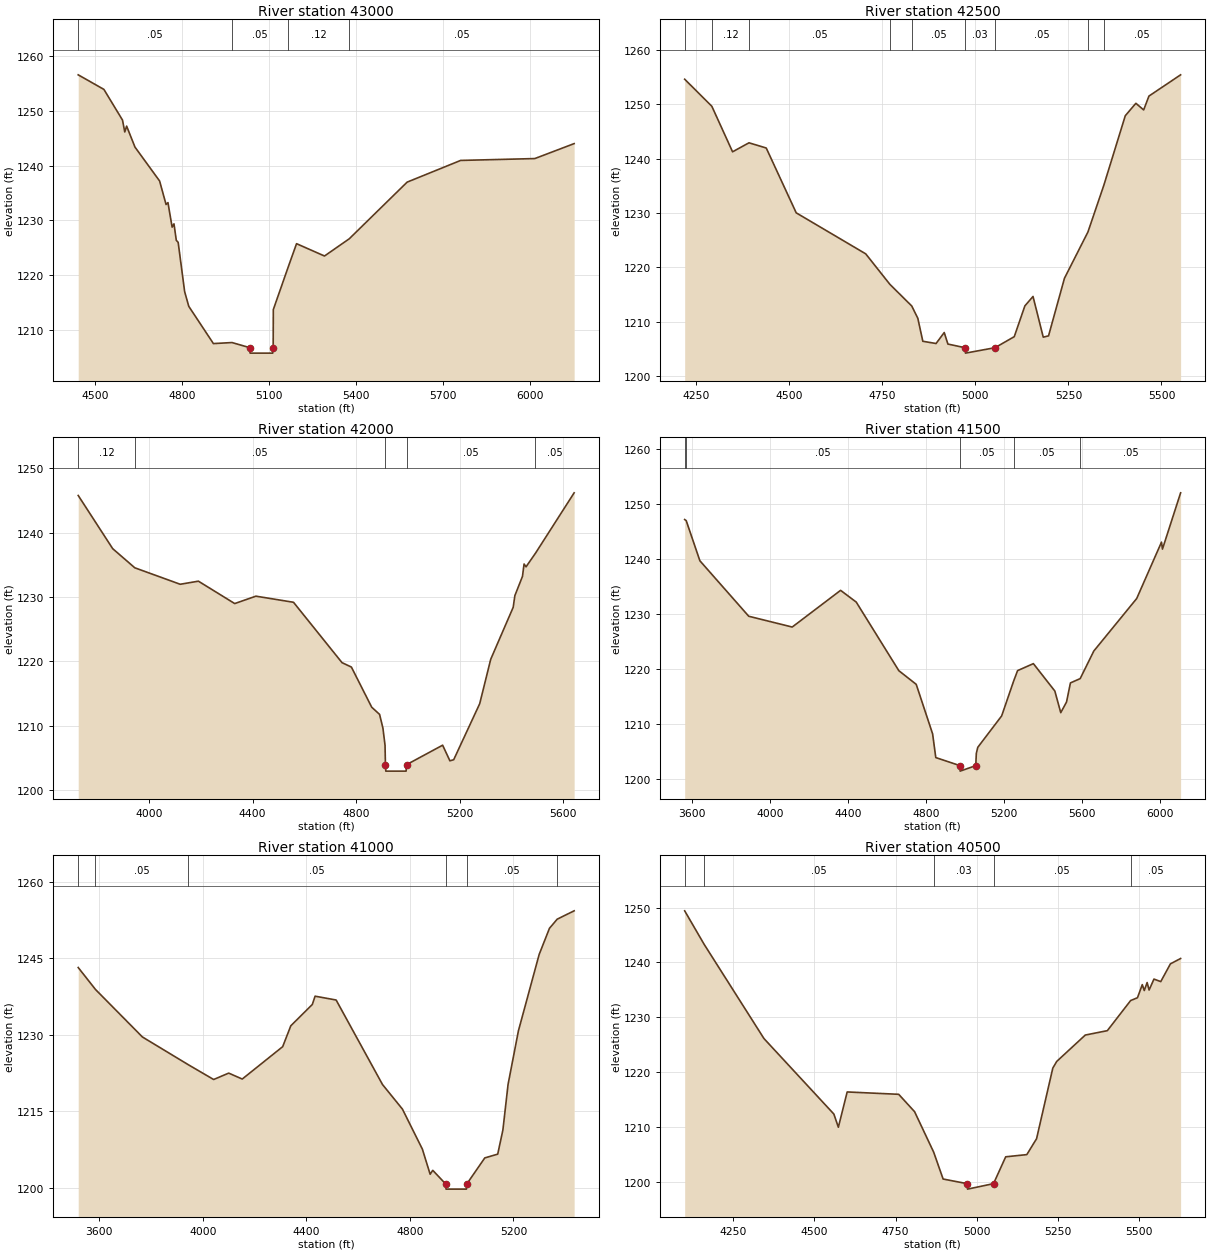
Type RM Length L Ch R = 1 ,43000   ,500,500,500
BEGIN DESCRIPTION:
HICKORY CREEK 86.0
END DESCRIPTION:
XS GIS Cut Line= 4
      2753447.73      10205500.4      2753796.53     10205066.01
      2753927.45     10204490.23      2753587.61     10204041.59
#Sta/Elev= 30
  4442.9 1256.56  4531.5  1253.9  4595.6 1248.31  4603.5 1246.13  4609.9  1247.2
  4638.7 1243.37  4723.6 1237.19  4745.9  1232.9  4752.4 1233.24  4766.8 1228.77
  4773.2 1229.37  4781.2 1226.36  4787.6    1226    4810 1216.99  4824.2 1214.32
  4909.2 1207.52  4973.2 1207.71  5034.3 1206.78  5035.8 1205.78  5113.8 1205.78
  5115.3 1206.78  5115.8 1213.73  5167.6 1221.56  5195.9 1225.75  5292.3  1223.5
  5377.6 1226.64  5577.3 1236.98  5761.8 1240.94  6017.7 1241.28  6153.3 1244.01
#Mann= 4 ,-1 , 0
  4442.9     .05       0  4973.2     .05       0  5167.6     .12       0
  5377.6     .05       0
Bank Sta=5034.3,5115.3
XS Rating Curve= 0 ,0
Exp/Cntr=0.3,0.1

Type RM Length L Ch R = 1 ,42500   ,500,500,500
BEGIN DESCRIPTION:
HICKORY CREEK 85.0
END DESCRIPTION:
XS GIS Cut Line= 4
      2753467.69     10205620.35      2753797.43     10205585.38
      2754188.52     10205363.77      2754605.72     10205003.08
#Sta/Elev= 30
  4218.9 1254.65  4291.9 1249.67  4347.6 1241.29  4391.7 1242.95  4438.1 1241.99
  4518.6 1230.06  4705.4 1222.51  4770.3  1216.9  4829.1 1212.91  4845.4 1210.64
  4858.8 1206.42  4894.4 1206.01  4916.3 1208.03  4926.2 1205.91  4971.9 1205.24
  4973.4 1204.24  5052.9 1205.24  5104.5 1207.27    5133 1212.93  5154.9 1214.67
  5182.4 1207.18  5196.6 1207.42  5239.4 1218.02  5302.5 1226.54  5345.2 1235.14
  5402.8 1247.93  5431.3 1250.22  5452.2    1249  5466.4 1251.55  5551.5 1255.46
#Mann= 9 ,-1 , 0
  4218.9     .05       0  4291.9     .12       0  4391.7     .05       0
  4770.3     .12       0  4829.1     .05       0  4971.9     .03       0
  5052.9     .05       0  5302.5     .12       0  5345.2     .05       0
Bank Sta=4971.9,5052.9
XS Rating Curve= 0 ,0
Exp/Cntr=0.3,0.1

Type RM Length L Ch R = 1 ,42000   ,500,500,500
BEGIN DESCRIPTION:
HICKORY CREEK 84.0
END DESCRIPTION:
XS GIS Cut Line= 4
      2753252.81     10206149.94      2753915.46     10206102.07
      2754426.67     10205771.23      2754805.66     10205253.15
#Sta/Elev= 30
  3726.7 1245.76  3859.9 1237.49  3945.2 1234.52  4120.6 1231.96  4190.8 1232.44
  4331.1 1228.96    4413 1230.11  4558.1 1229.16  4745.4 1219.78  4781.7 1219.09
  4860.2 1212.85  4890.5 1211.74  4903.5 1209.59  4911.6 1206.93  4913.1 1203.92
  4914.6 1202.92    4993 1202.92  4994.5 1203.92    5134 1206.95  5162.1 1204.52
  5176.7 1204.69  5277.1 1213.39  5319.8 1220.31  5406.5 1228.38    5413  1230.2
  5442.3 1233.18  5448.5 1235.11  5456.1 1234.67  5492.5 1236.78  5641.9 1246.17
#Mann= 5 ,-1 , 0
  3726.7     .12       0  3945.2     .05       0  4913.1     .05       0
  4994.5     .05       0  5492.5     .05       0
Bank Sta=4913.1,4994.5
XS Rating Curve= 0 ,0
Exp/Cntr=0.3,0.1

Type RM Length L Ch R = 1 ,41500   ,500,500,500
BEGIN DESCRIPTION:
HICKORY CREEK 83.0
END DESCRIPTION:
XS GIS Cut Line= 5
      2753257.85     10206219.89      2754260.89      10206289.9
      2754681.53     10206189.23      2754996.51     10206124.96
       2755780.8     10206139.95
#Sta/Elev= 30
    3562 1247.11  3569.9 1246.91    3640 1239.63  3890.6 1229.56  4113.6  1227.6
  4361.8 1234.26    4442 1232.13  4660.5 1219.68  4749.7  1217.2  4833.8 1208.21
    4850 1203.91  4973.7 1202.45  4975.2 1201.45  5055.1 1202.45    5058 1204.68
  5065.5 1205.77  5187.9 1211.47  5249.2 1217.77  5269.6 1219.69  5350.6 1220.96
  5460.7 1215.99  5491.1 1212.06  5520.7 1213.99  5540.7 1217.46  5590.7 1218.24
  5660.7 1223.25  5880.7 1232.78  6007.8 1243.01  6012.8 1241.75  6105.9 1251.96
#Mann= 5 ,-1 , 0
    3562     .12       0  3569.9     .05       0  4973.7     .05       0
  5249.2     .05       0  5590.7     .05       0
Bank Sta=4973.7,5055.1
XS Rating Curve= 0 ,0
Exp/Cntr=0.3,0.1

Type RM Length L Ch R = 1 ,41000   ,500,500,500
BEGIN DESCRIPTION:
HICKORY CREEK 82.0
END DESCRIPTION:
XS GIS Cut Line= 4
      2753247.89     10206329.81      2754142.17      10206594.6
      2754686.29     10206669.45      2755121.06     10206674.53
#Sta/Elev= 30
  3518.1 1243.17  3584.6 1238.89  3766.1 1229.58  3943.4 1224.15  4041.5 1221.25
  4099.8  1222.5    4152 1221.34  4308.4 1227.68  4339.7 1231.76  4422.9 1235.94
  4433.6 1237.56  4514.9 1236.81  4694.1 1220.27  4771.2 1215.45  4848.2 1207.62
  4878.3  1202.7  4888.4 1203.47  4938.4 1200.79  4939.9 1199.79  5018.4 1199.79
  5019.9 1200.79  5089.4  1205.9  5139.4 1206.64  5159.4 1211.36  5179.4 1220.29
  5219.4 1230.78  5299.4  1245.7  5339.4 1250.85  5369.4 1252.64  5434.8 1254.27
#Mann= 6 ,-1 , 0
  3518.1     .12       0  3584.6     .05       0  3943.4     .05       0
  4938.4     .03       0  5019.9     .05       0  5369.4     .05       0
Bank Sta=4938.4,5019.9
XS Rating Curve= 0 ,0
Exp/Cntr=0.3,0.1

Type RM Length L Ch R = 1 ,40500   ,500,500,500
BEGIN DESCRIPTION:
HICKORY CREEK 81.0
END DESCRIPTION:
XS GIS Cut Line= 4
      2753777.46     10207339.02      2754655.11     10207146.62
       2755001.5     10207074.23      2755156.39     10206849.38
#Sta/Elev= 30
  4101.5  1249.4  4161.1 1243.32  4345.4 1226.12  4560.4 1212.36  4574.2 1209.96
  4601.3 1216.39  4759.8 1215.96  4808.7 1212.79  4867.5  1205.4  4896.4 1200.52
    4970 1199.68  4971.5 1198.68  5051.5 1199.68  5088.9 1204.57  5153.8 1204.97
  5183.8 1207.86  5233.8 1220.74  5245.8 1221.95  5333.7 1226.76  5401.5 1227.56
  5473.2 1233.05  5494.2 1233.56    5509 1235.95  5515.1 1234.87  5523.9 1236.33
    5530 1234.97  5544.9 1236.96  5565.8  1236.5  5595.6 1239.74  5626.9 1240.71
#Mann= 5 ,-1 , 0
  4101.5     .05       0  4161.1     .05       0  4867.5     .03       0
  5051.5     .05       0  5473.2     .05       0
Bank Sta=4970,5051.5
XS Rating Curve= 0 ,0
Exp/Cntr=0.3,0.1

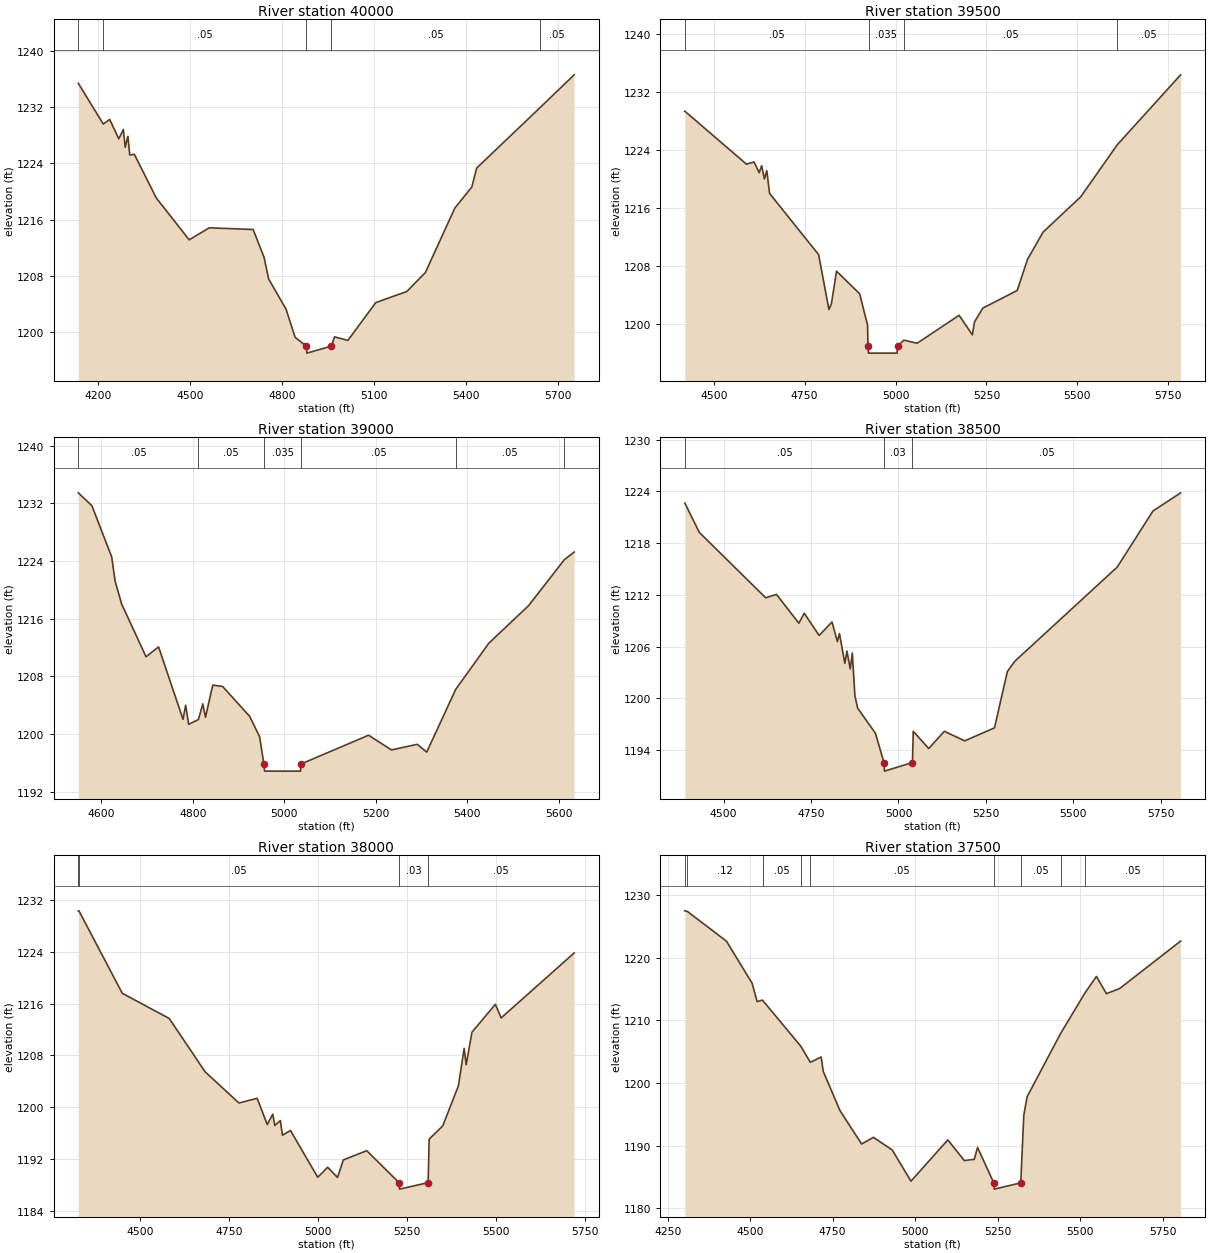
Type RM Length L Ch R = 1 ,40000   ,500,500,500
BEGIN DESCRIPTION:
HICKORY CREEK 80.0
END DESCRIPTION:
XS GIS Cut Line= 3
      2754032.28      10208113.4      2754741.82     10207618.65
      2755486.08     10207513.89
#Sta/Elev= 30
    4135 1235.43  4216.3 1229.62  4237.2 1230.28  4266.9 1227.51  4281.7 1228.84
  4287.8 1226.32  4296.6 1227.87  4302.7  1225.2  4317.5 1225.31    4389 1219.09
  4496.4 1213.11  4561.8 1214.82  4704.9 1214.58  4740.6 1210.62  4755.5 1207.52
  4812.2 1203.23  4841.9  1199.2  4878.7 1197.95  4880.2 1196.95  4960.3 1197.95
  4970.1 1199.27    5014 1198.77  5104.9 1204.16  5205.9 1205.74  5266.5 1208.44
  5362.5 1217.63  5417.9 1220.64  5433.7 1223.34  5640.1 1231.95  5751.6 1236.64
#Mann= 5 ,-1 , 0
    4135     .05       0  4216.3     .05       0  4878.7     .03       0
  4960.3     .05       0  5640.1     .05       0
Bank Sta=4878.7,4960.3
XS Rating Curve= 0 ,0
Exp/Cntr=0.3,0.1

Type RM Length L Ch R = 1 ,39500   ,500,500,500
BEGIN DESCRIPTION:
HICKORY CREEK 79.0
END DESCRIPTION:
XS GIS Cut Line= 3
      2754396.97     10208463.15      2754832.65     10208081.05
      2755496.13     10207663.76
#Sta/Elev= 30
  4420.5  1229.4    4590 1222.09  4610.9 1222.39  4625.1 1220.91  4631.8 1221.87
  4639.4 1220.05    4646  1221.2  4653.6 1218.05  4788.4 1209.61  4816.8 1202.04
  4823.5  1202.8  4837.7 1207.32  4901.3 1204.21  4923.1 1199.85  4924.1 1197.02
  4925.6 1196.02  5004.2 1196.02  5005.7 1197.02  5022.8 1197.81  5059.3 1197.38
  5174.7 1201.24  5211.2 1198.55  5217.1 1200.33  5239.9 1202.23  5334.4 1204.66
  5363.1 1208.99  5405.6 1212.71  5509.2 1217.59  5609.3 1224.74  5783.8 1234.41
#Mann= 4 ,-1 , 0
  4420.5     .05       0  4925.6    .035       0  5022.8     .05       0
  5609.3     .05       0
Bank Sta=4924.1,5005.7
XS Rating Curve= 0 ,0
Exp/Cntr=0.3,0.1

Type RM Length L Ch R = 1 ,39000   ,500,500,500
BEGIN DESCRIPTION:
HICKORY CREEK 78.0
END DESCRIPTION:
XS GIS Cut Line= 3
      2754905.69     10208853.11      2755127.37     10208461.04
      2755505.67     10207953.14
#Sta/Elev= 30
  4549.6 1233.44  4579.2 1231.66  4622.5 1224.56    4630 1221.19  4644.1 1218.05
  4697.6 1210.71    4725 1212.08  4778.4 1202.03  4784.2 1203.99  4790.8 1201.34
    4812    1202  4821.7 1204.18  4827.5 1202.31  4843.4 1206.78    4865 1206.59
  4924.2 1202.44  4945.8 1199.61  4955.1 1195.85  4956.6 1194.85  5035.2 1194.85
  5036.7 1195.85    5184 1199.83    5234 1197.79  5290.3 1198.57  5311.1 1197.49
  5374.5 1206.19  5446.7 1212.58  5533.6 1217.79  5611.9 1224.17  5633.3 1225.23
#Mann= 6 ,-1 , 0
  4549.6     .05       0    4812     .05       0  4955.1    .035       0
  5036.7     .05       0  5374.5     .05       0  5611.9     .05       0
Bank Sta=4955.1,5036.7
XS Rating Curve= 0 ,0
Exp/Cntr=0.3,0.1

Type RM Length L Ch R = 1 ,38500   ,500,500,500
BEGIN DESCRIPTION:
HICKORY CREEK 77.0
END DESCRIPTION:
XS GIS Cut Line= 3
      2755251.29     10209177.63      2755570.38     10208656.93
      2755990.69     10207968.61
#Sta/Elev= 30
  4389.3 1222.65    4431 1219.24  4620.6 1211.67  4651.4 1212.06  4715.3 1208.72
  4730.7 1209.88  4773.3  1207.3  4810.1 1208.86  4825.5 1206.59  4831.4 1207.53
  4846.8 1204.06  4852.7  1205.5  4862.2 1203.42  4868.1 1205.27  4875.5 1200.31
  4883.5 1198.86  4934.1 1195.97  4958.5 1192.57    4960 1191.57  5040.1 1192.57
  5042.2 1196.19  5086.5 1194.19  5131.2 1196.19  5189.3 1195.08  5274.5 1196.59
  5311.3 1203.12  5332.6 1204.31  5625.5 1215.24  5727.4 1221.73  5806.5 1223.84
#Mann= 3 ,-1 , 0
  4389.3     .05       0  4958.5     .03       0  5040.1     .05       0
Bank Sta=4958.5,5040.1
XS Rating Curve= 0 ,0
Exp/Cntr=0.3,0.1

Type RM Length L Ch R = 1 ,38000   ,500,500,500
BEGIN DESCRIPTION:
HICKORY CREEK 76.0
END DESCRIPTION:
XS GIS Cut Line= 3
      2755645.99     10209452.42      2755995.02       10208877.
      2756335.45     10208243.36
#Sta/Elev= 30
    4327 1230.34  4328.7 1230.34  4450.4  1217.6  4582.2 1213.71    4683 1205.47
    4778 1200.65  4829.1 1201.37  4857.5 1197.32    4873 1198.92  4878.8 1197.18
  4894.3 1197.93  4900.2 1195.67  4922.7  1196.4  4999.3 1189.17  5027.1 1190.72
  5054.9 1189.14  5071.1 1191.85  5136.9 1193.28  5227.5 1188.34    5229 1187.34
  5309.2 1188.34  5312.2 1195.07  5350.3 1197.11  5394.2 1203.29  5410.4 1209.09
  5416.1 1206.56  5432.3 1211.58  5498.1  1215.9  5514.3 1213.79  5719.3 1223.83
#Mann= 4 ,-1 , 0
    4327     .12       0  4328.7     .05       0  5227.5     .03       0
  5309.2     .05       0
Bank Sta=5227.5,5309.2
XS Rating Curve= 0 ,0
Exp/Cntr=0.3,0.1

Type RM Length L Ch R = 1 ,37500   ,500,500,500
BEGIN DESCRIPTION:
HICKORY CREEK 75.0
END DESCRIPTION:
XS GIS Cut Line= 3
      2756025.71     10209667.22      2756420.87     10209091.85
      2756390.43     10208288.33
#Sta/Elev= 30
    4302  1227.5  4309.9  1227.4  4428.3 1222.65  4506.1 1215.93    4521 1213.02
  4537.4 1213.24  4653.2 1205.91  4682.3 1203.32  4715.2 1204.17  4721.3 1201.89
    4772 1195.63  4837.7 1190.28  4873.6 1191.34  4930.4 1189.33  4987.2 1184.35
  5098.8 1190.94  5148.8 1187.64  5178.9 1187.83  5188.9 1189.73  5238.1 1184.08
  5239.6 1183.08  5319.8 1184.08    5329 1194.86    5339 1197.82  5440.4 1207.91
  5514.4  1214.4  5549.1 1217.03  5579.2 1214.28  5619.2 1215.09  5804.1 1222.67
#Mann= 9 ,-1 , 0
    4302     .05       0  4309.9     .12       0  4537.4     .05       0
  4653.2     .12       0  4682.3     .05       0  5238.1     .03       0
  5319.8     .05       0  5440.4     .12       0  5514.4     .05       0
Bank Sta=5238.1,5319.8
XS Rating Curve= 0 ,0
Exp/Cntr=0.3,0.1

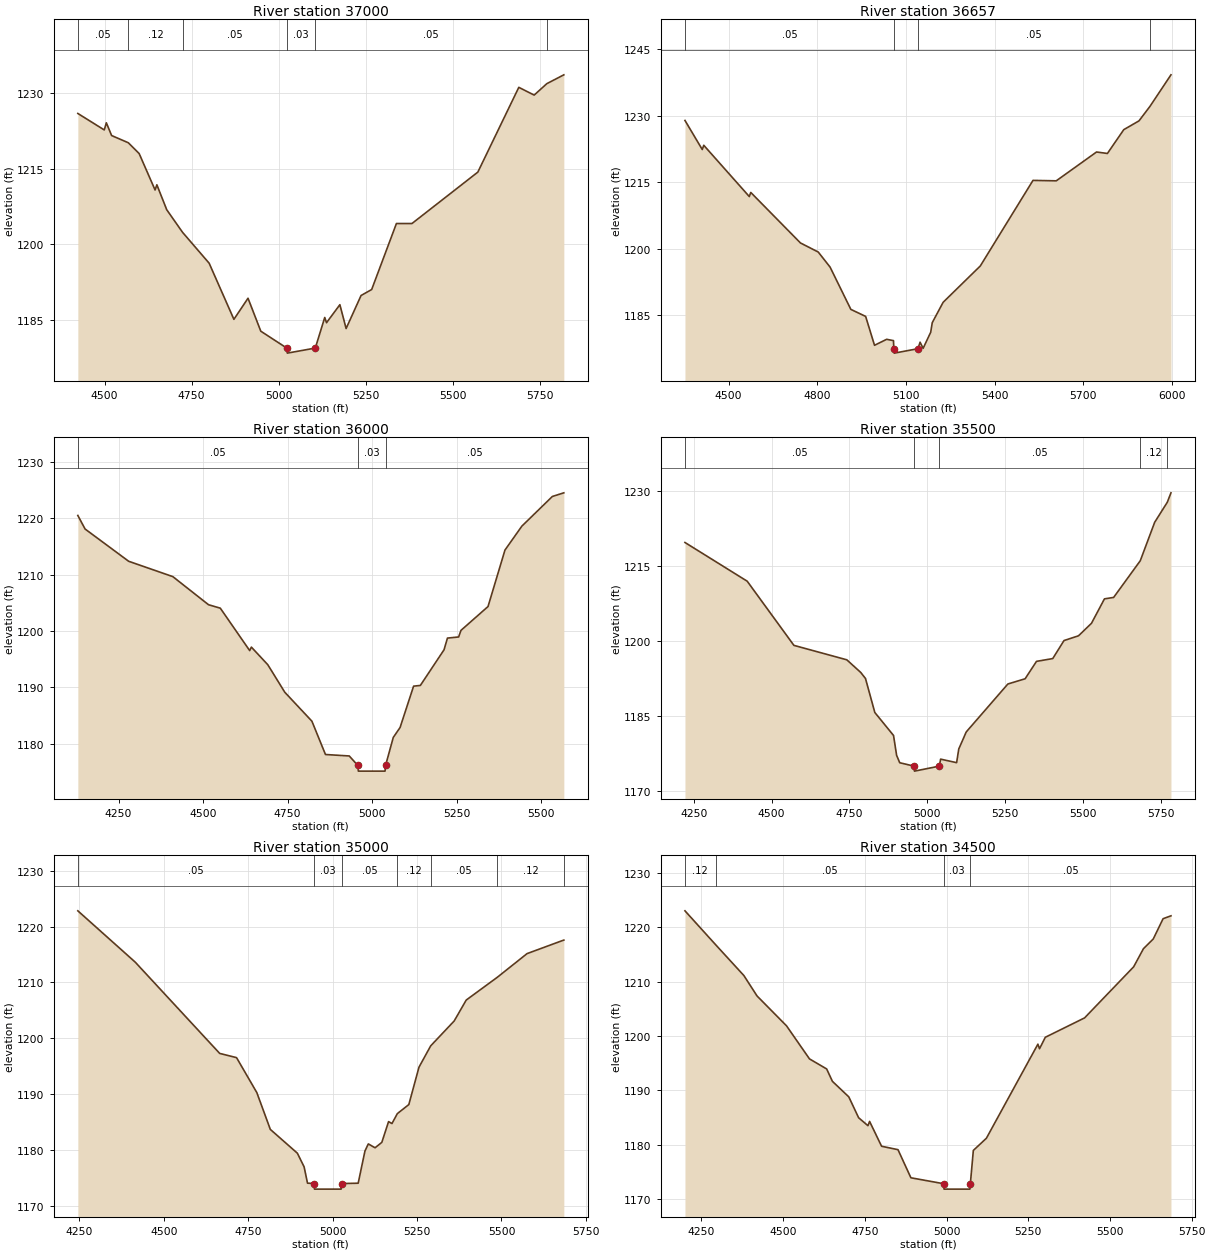
Type RM Length L Ch R = 1 ,37000   ,343,343,343
BEGIN DESCRIPTION:
HICKORY CREEK 74.0
END DESCRIPTION:
XS GIS Cut Line= 4
       2756060.7      10209682.2      2756204.61     10209586.53
      2756602.75     10209519.79      2757409.67     10209387.44
#Sta/Elev= 30
  4423.5 1225.94  4499.3 1222.68  4505.3 1224.09  4520.4 1221.57  4568.3 1220.14
  4599.4    1218  4645.1 1210.79  4650.2 1211.82  4678.5 1206.88    4724  1202.4
  4800.2 1196.29  4871.2 1185.18  4911.7 1189.36  4948.4 1182.83  5022.9 1179.49
  5024.4 1178.49  5104.7 1179.49  5131.8 1185.55  5136.9 1184.51  5175.2 1188.08
  5193.1 1183.36    5236  1189.9  5266.4 1191.08  5337.4 1204.15    5382 1204.15
    5571 1214.33  5688.5 1231.11  5732.6 1229.58  5768.9 1231.84  5817.7 1233.59
#Mann= 6 ,-1 , 0
  4423.5     .05       0  4568.3     .12       0    4724     .05       0
  5022.9     .03       0  5104.7     .05       0  5768.9     .12       0
Bank Sta=5022.9,5104.7
XS Rating Curve= 0 ,0
Exp/Cntr=0.3,0.1

Type RM Length L Ch R = 1 ,36657   ,657,657,657
BEGIN DESCRIPTION:
HICKORY CREEK 73.0
END DESCRIPTION:
XS GIS Cut Line= 3
      2755965.75     10209902.04      2756612.25       10209861.
      2757580.85     10209628.13
#Sta/Elev= 30
  4352.2 1228.98  4410.7 1222.41  4415.8 1223.37  4569.8 1211.79  4574.8 1212.72
  4742.9 1201.31    4803 1199.26  4843.1 1195.86  4913.3 1186.31  4963.4 1184.72
  4993.4  1178.2  5034.4 1179.55  5057.6 1179.25  5058.7 1177.43  5060.2 1176.43
  5140.5 1177.43  5147.5  1178.9  5157.8 1177.51  5183.5 1181.15  5188.7 1183.31
  5225.5 1187.91  5351.3 1196.12  5529.5 1215.44  5608.2 1215.34  5744.4 1221.85
  5781.2 1221.52  5836.6  1226.9    5888 1228.88  5925.4 1232.18  5996.2 1239.28
#Mann= 4 ,-1 , 0
  4352.2     .05       0  5058.7     .03       0  5140.5     .05       0
  5925.4     .12       0
Bank Sta=5058.7,5140.5
XS Rating Curve= 0 ,0
Exp/Cntr=0.3,0.1

Type RM Length L Ch R = 1 ,36000   ,500,500,500
BEGIN DESCRIPTION:
HICKORY CREEK 72.0
END DESCRIPTION:
XS GIS Cut Line= 3
      2755925.76     10210386.67      2756793.18     10210457.43
       2757359.7     10210436.63
#Sta/Elev= 30
  4129.7 1220.51  4151.1 1218.11  4280.1 1212.38  4410.6 1209.66  4516.2 1204.67
    4551 1204.06  4637.9 1196.53  4642.9 1197.15  4691.5 1194.02  4741.7 1189.14
  4821.9    1184    4862 1178.09  4932.3 1177.83  4957.8 1176.14  4959.3 1175.14
  5038.2 1175.14  5039.7 1176.14  5062.5 1181.12  5082.6 1182.88  5122.6 1190.22
  5142.6 1190.35  5212.6 1196.67  5222.7 1198.75  5255.8 1198.95  5262.7 1200.12
  5342.7 1204.35  5392.8 1214.37  5442.8 1218.62  5532.9 1223.88  5566.9 1224.53
#Mann= 3 ,-1 , 0
  4129.7     .05       0  4957.8     .03       0  5039.7     .05       0
Bank Sta=4957.8,5039.7
XS Rating Curve= 0 ,0
Exp/Cntr=0.3,0.1

Type RM Length L Ch R = 1 ,35500   ,500,500,500
BEGIN DESCRIPTION:
HICKORY CREEK 71.0
END DESCRIPTION:
XS GIS Cut Line= 3
      2755925.77     10210926.25       2756704.1     10210942.61
      2757464.63     10210756.38
#Sta/Elev= 30
  4221.5 1219.64  4421.5 1211.92  4571.5 1199.13  4741.5 1196.25  4786.3 1193.73
  4801.5 1192.53  4831.5 1185.75  4891.6 1181.17  4901.6 1177.19  4911.6 1175.73
  4957.3 1175.06  4958.8 1174.06  5039.2 1175.06  5042.8 1176.45  5094.3 1175.75
  5101.2 1178.47  5125.2 1181.87    5259 1191.43  5314.4 1192.47  5350.9 1195.94
  5403.2  1196.5  5439.3 1200.09    5486 1201.04  5527.6 1203.53  5569.3  1208.4
  5598.8 1208.69  5684.4    1216  5730.6 1223.66  5771.3 1227.67    5783 1229.54
#Mann= 5 ,-1 , 0
  4221.5     .05       0  4957.3     .03       0  5039.2     .05       0
  5684.4     .12       0  5771.3     .05       0
Bank Sta=4957.3,5039.2
XS Rating Curve= 0 ,0
Exp/Cntr=0.3,0.1

Type RM Length L Ch R = 1 ,35000   ,500,500,500
BEGIN DESCRIPTION:
HICKORY CREEK 70.0
END DESCRIPTION:
XS GIS Cut Line= 3
      2755895.83     10211405.88      2756650.05     10211429.57
      2757334.66     10211445.85
#Sta/Elev= 30
  4245.4 1222.81  4415.3 1213.62  4665.5 1197.26  4715.5  1196.5  4775.5 1190.24
  4815.5 1183.64  4895.6 1179.38  4915.6 1176.92  4925.6 1174.01  4944.7 1173.94
  4946.2 1172.94  5025.1 1172.94  5026.6 1173.94  5075.7    1174  5095.7 1179.76
  5105.7 1181.04  5125.7 1180.35  5145.7 1181.32  5165.7 1185.04  5175.7 1184.69
  5191.7 1186.47  5225.7 1188.09  5255.7 1194.78  5290.4 1198.61    5360 1203.07
  5395.7 1206.82  5487.7  1210.9  5575.8 1215.14  5684.2 1217.56  5684.8 1217.56
#Mann= 7 ,-1 , 0
  4245.4     .05       0  4944.7     .03       0  5026.6     .05       0
  5191.7     .12       0  5290.4     .05       0  5487.7     .12       0
  5684.2     .05       0
Bank Sta=4944.7,5026.6
XS Rating Curve= 0 ,0
Exp/Cntr=0.3,0.1

Type RM Length L Ch R = 1 ,34500   ,500,500,500
BEGIN DESCRIPTION:
HICKORY CREEK 69.0
END DESCRIPTION:
XS GIS Cut Line= 3
      2755825.88     10211835.55      2756623.69     10211896.01
      2757309.76     10211925.48
#Sta/Elev= 30
  4199.9 1223.06  4294.1 1216.79  4380.2 1211.13  4420.3 1207.38  4510.6 1201.87
  4580.8 1195.78  4633.4 1193.92    4651 1191.64  4701.1 1188.78  4731.2 1184.93
  4759.7 1183.47  4764.7 1184.26  4801.4 1179.68  4851.6 1179.05  4891.1 1173.87
  4991.1 1172.78  4992.6 1171.78  5071.5 1171.78    5073 1172.78  5082.1 1178.91
  5122.1 1181.16  5279.6 1198.49  5284.6 1197.65  5302.3 1199.76  5422.4 1203.33
  5572.5 1212.74  5602.5 1216.08  5632.6 1217.88  5662.6 1221.61  5686.7 1222.14
#Mann= 4 ,-1 , 0
  4199.9     .12       0  4294.1     .05       0  4991.1     .03       0
    5073     .05       0
Bank Sta=4991.1,5073
XS Rating Curve= 0 ,0
Exp/Cntr=0.3,0.1

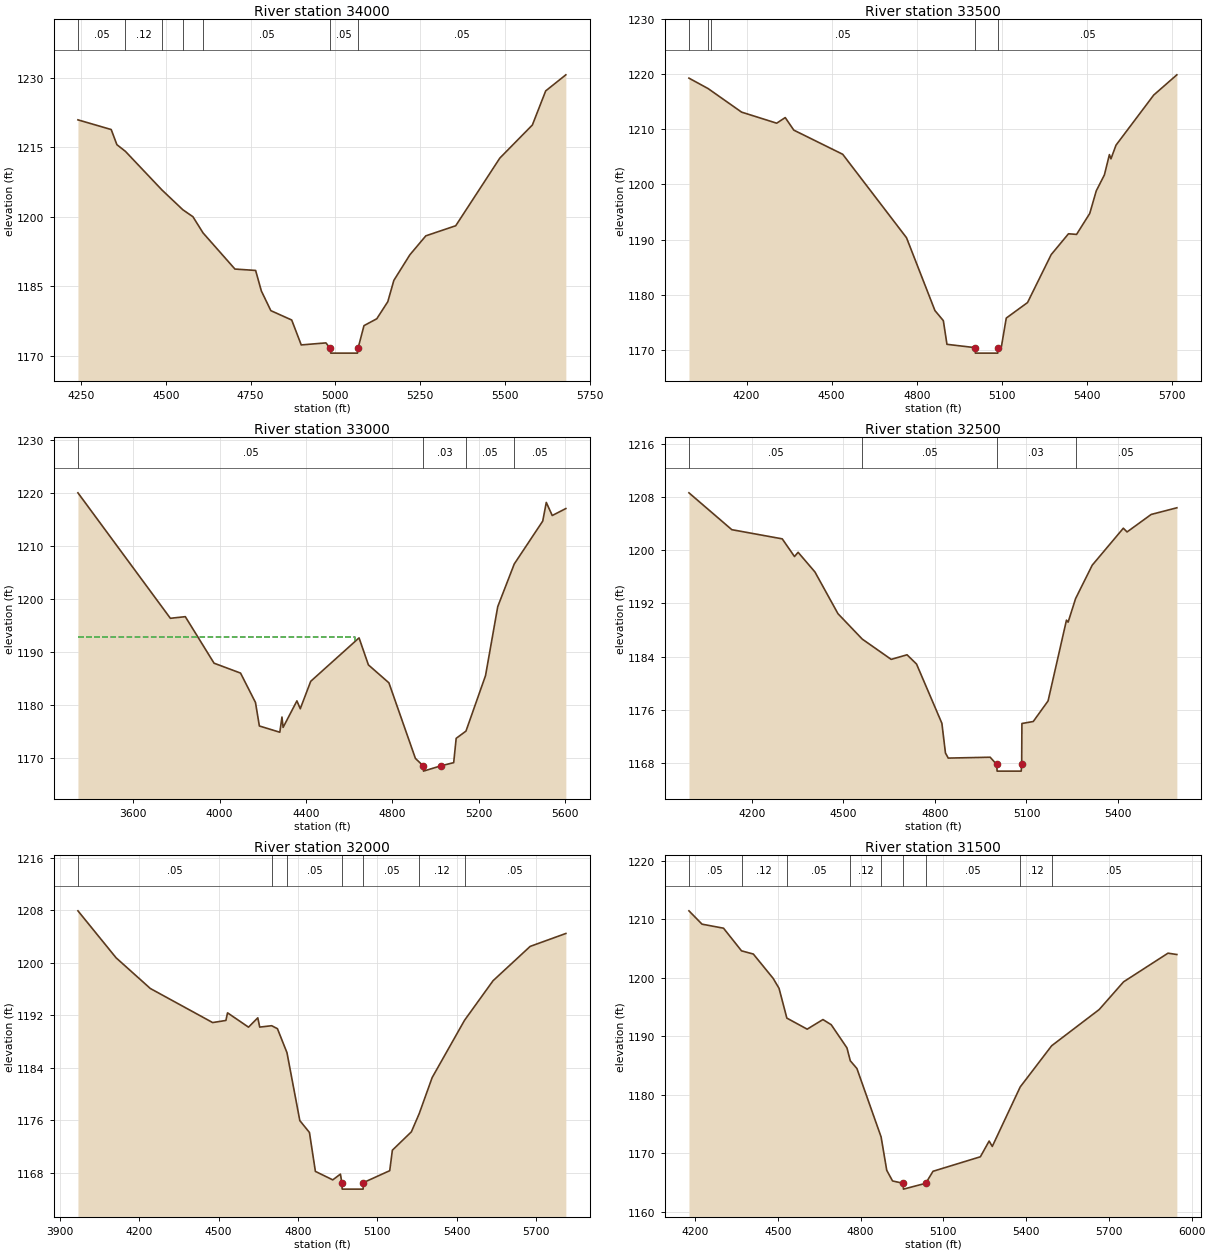
Type RM Length L Ch R = 1 ,34000   ,500,500,500
BEGIN DESCRIPTION:
HICKORY CREEK 68.0
END DESCRIPTION:
XS GIS Cut Line= 3
      2755800.92     10211985.45      2756481.17     10212322.78
      2757129.88     10212525.02
#Sta/Elev= 30
  4240.7 1220.93  4338.8 1218.84  4355.6 1215.57  4380.7 1214.13  4488.5 1205.79
  4550.1 1201.52  4579.8 1200.02  4609.8 1196.51  4703.7 1188.72  4764.7 1188.42
  4781.6 1183.99  4809.6 1179.74  4871.1 1177.72  4899.2 1172.34  4972.1 1172.78
  4984.7 1171.57  4986.2 1170.57  5065.1 1170.57  5066.6 1171.57  5084.2  1176.5
    5122 1177.99  5154.5 1181.68  5172.3 1186.27  5219.5 1191.79  5266.6 1195.89
  5354.8 1198.07  5484.8 1212.67  5580.8 1219.82  5620.1 1227.18  5679.5 1230.65
#Mann= 7 ,-1 , 0
  4240.7     .05       0  4380.7     .12       0  4488.5     .05       0
  4550.1     .12       0  4609.8     .05       0  4984.7     .05       0
  5066.6     .05       0
Bank Sta=4984.7,5066.6
XS Rating Curve= 0 ,0
Exp/Cntr=0.3,0.1

Type RM Length L Ch R = 1 ,33500   ,500,500,500
BEGIN DESCRIPTION:
HICKORY CREEK 67.0
END DESCRIPTION:
XS GIS Cut Line= 4
       2755780.9     10212015.38      2755831.42     10212491.83
      2756275.48     10212770.35      2756929.98     10213064.59
#Sta/Elev= 30
  3996.7 1219.33  4064.3 1217.43  4074.5 1217.06  4182.4 1213.15  4306.2 1211.14
  4336.3 1212.16  4366.5 1209.88    4539 1205.49  4764.1 1190.32  4864.3 1177.09
    4894 1175.25  4906.7 1170.95  5005.5 1170.35    5007 1169.35  5085.9 1169.35
  5087.4 1170.35  5098.9 1170.57  5115.9 1175.72  5190.9 1178.54  5274.3 1187.25
  5335.3 1191.04  5363.9 1190.93  5410.3 1194.73  5433.4 1198.85  5462.1 1201.75
  5479.7 1205.43  5485.2 1204.66  5502.9 1207.14  5636.1 1216.26  5717.6 1219.93
#Mann= 5 ,-1 , 0
  3996.7     .05       0  4064.3     .12       0  4074.5     .05       0
  5005.5     .05       0  5087.4     .05       0
Bank Sta=5005.5,5087.4
XS Rating Curve= 0 ,0
Exp/Cntr=0.3,0.1

Type RM Length L Ch R = 1 ,33000   ,500,500,500
BEGIN DESCRIPTION:
HICKORY CREEK 66.0
END DESCRIPTION:
XS GIS Cut Line= 3
      2754486.92     10212694.89      2756061.53     10213206.38
      2756594.15     10213488.68
#Sta/Elev= 30
  3344.4 1220.01  3772.3 1196.33  3841.4 1196.64  3974.5 1187.86  4097.1 1185.99
  4166.3 1180.44  4184.2 1176.01  4278.9 1174.83  4288.8  1177.7  4294.1 1175.74
    4358 1180.75  4373.5 1179.26  4421.9 1184.44  4645.6 1192.64  4688.9 1187.54
  4783.9 1184.15  4906.5 1169.89  4942.4 1168.49  4943.9 1167.49  5024.3 1168.49
  5083.7 1169.09  5095.2 1173.68  5140.5 1175.04  5231.1 1185.52  5287.6 1198.53
    5364 1206.58  5495.9 1214.68  5512.3  1218.2  5539.9 1215.73  5602.8 1217.04
#Mann= 4 ,-1 , 0
  3344.4     .05       0  4942.4     .03       0  5140.5     .05       0
    5364     .05       0
#XS Ineff= 2 , 0
         4628.42 1192.85
Permanent Ineff=
       F       F
Bank Sta=4942.4,5024.3
XS Rating Curve= 0 ,0
Exp/Cntr=0.3,0.1

Type RM Length L Ch R = 1 ,32500   ,500,500,500
BEGIN DESCRIPTION:
HICKORY CREEK 65.0
END DESCRIPTION:
XS GIS Cut Line= 4
      2754901.55     10213269.43      2755446.16     10213524.25
      2755836.34       10213634.      2756389.28     10213848.55
#Sta/Elev= 30
  3993.4 1208.63  4133.9 1203.09  4299.3 1201.71  4339.5 1199.05  4351.3 1199.69
  4406.5 1196.73    4482 1190.46  4561.6 1186.64  4656.5 1183.59  4708.4 1184.28
  4739.6 1182.89  4822.7 1173.98  4834.4 1169.52  4843.5 1168.75    4981 1168.88
  5002.3 1167.79  5003.8 1166.79  5082.8 1166.79  5084.3 1167.79  5085.1 1173.95
  5122.3 1174.25  5170.9 1177.35  5231.2 1189.49  5236.6 1189.19  5261.1 1192.73
  5315.6 1197.75  5417.6 1203.31  5429.9 1202.75  5508.9 1205.38  5593.1 1206.38
#Mann= 4 ,-1 , 0
  3993.4     .05       0  4561.6     .05       0  5002.3     .03       0
  5261.1     .05       0
Bank Sta=5002.3,5084.3
XS Rating Curve= 0 ,0
Exp/Cntr=0.3,0.1

Type RM Length L Ch R = 1 ,32000   ,500,500,500
BEGIN DESCRIPTION:
HICKORY CREEK 64.0
END DESCRIPTION:
XS GIS Cut Line= 4
       2754886.6      10213329.4      2755294.06     10213877.46
      2755588.75     10214064.39      2756400.44     10214113.79
#Sta/Elev= 30
  3968.1 1207.93  4112.5 1200.77  4241.9  1196.1  4477.6 1190.91  4527.6 1191.23
  4533.9 1192.39  4613.2 1190.21  4648.2 1191.63  4655.6 1190.22  4700.7 1190.43
  4722.5 1189.98  4758.6 1186.33  4807.2 1175.98  4843.6 1174.17  4866.1 1168.24
  4931.8 1166.95  4960.8 1167.83    4966 1166.54  4967.5 1165.54  5046.5 1165.54
    5048 1166.54  5147.2 1168.35  5157.2 1171.47  5229.1 1174.27  5258.7 1177.04
  5307.5 1182.52    5430 1191.25  5537.9 1197.28  5678.2 1202.51  5813.2 1204.48
#Mann= 7 ,-1 , 0
  3968.1     .05       0  4700.7     .12       0  4758.6     .05       0
    4966     .05       0    5048     .05       0  5258.7     .12       0
    5430     .05       0
Bank Sta=4966,5048
XS Rating Curve= 0 ,0
Exp/Cntr=0.3,0.1

Type RM Length L Ch R = 1 ,31500   ,500,500,500
BEGIN DESCRIPTION:
HICKORY CREEK 63.0
END DESCRIPTION:
XS GIS Cut Line= 3
      2755081.42     10215232.96      2755538.65     10214550.11
      2756415.39     10214193.74
#Sta/Elev= 30
  4178.2 1211.45  4225.5 1209.17  4303.5 1208.48  4368.7 1204.61  4411.6 1204.06
  4483.7 1199.88  4504.7  1198.2    4533 1193.11  4606.7 1191.22  4663.8 1192.86
  4693.8 1191.98  4750.8 1188.02  4762.9 1185.82  4786.9 1184.49  4874.6 1172.79
    4895 1167.09    4916 1165.27  4954.1 1164.87  4955.6 1163.87  5036.3 1164.87
  5062.7 1166.92  5234.3  1169.4  5266.1 1172.09  5277.5 1171.17  5378.7 1181.34
  5492.6 1188.38  5664.9 1194.57  5753.3 1199.31  5914.3 1204.21  5946.4 1203.98
#Mann= 9 ,-1 , 0
  4178.2     .05       0  4368.7     .12       0    4533     .05       0
  4762.9     .12       0  4874.6     .05       0  4954.1     .03       0
  5036.3     .05       0  5378.7     .12       0  5492.6     .05       0
Bank Sta=4954.1,5036.3
XS Rating Curve= 0 ,0
Exp/Cntr=0.3,0.1

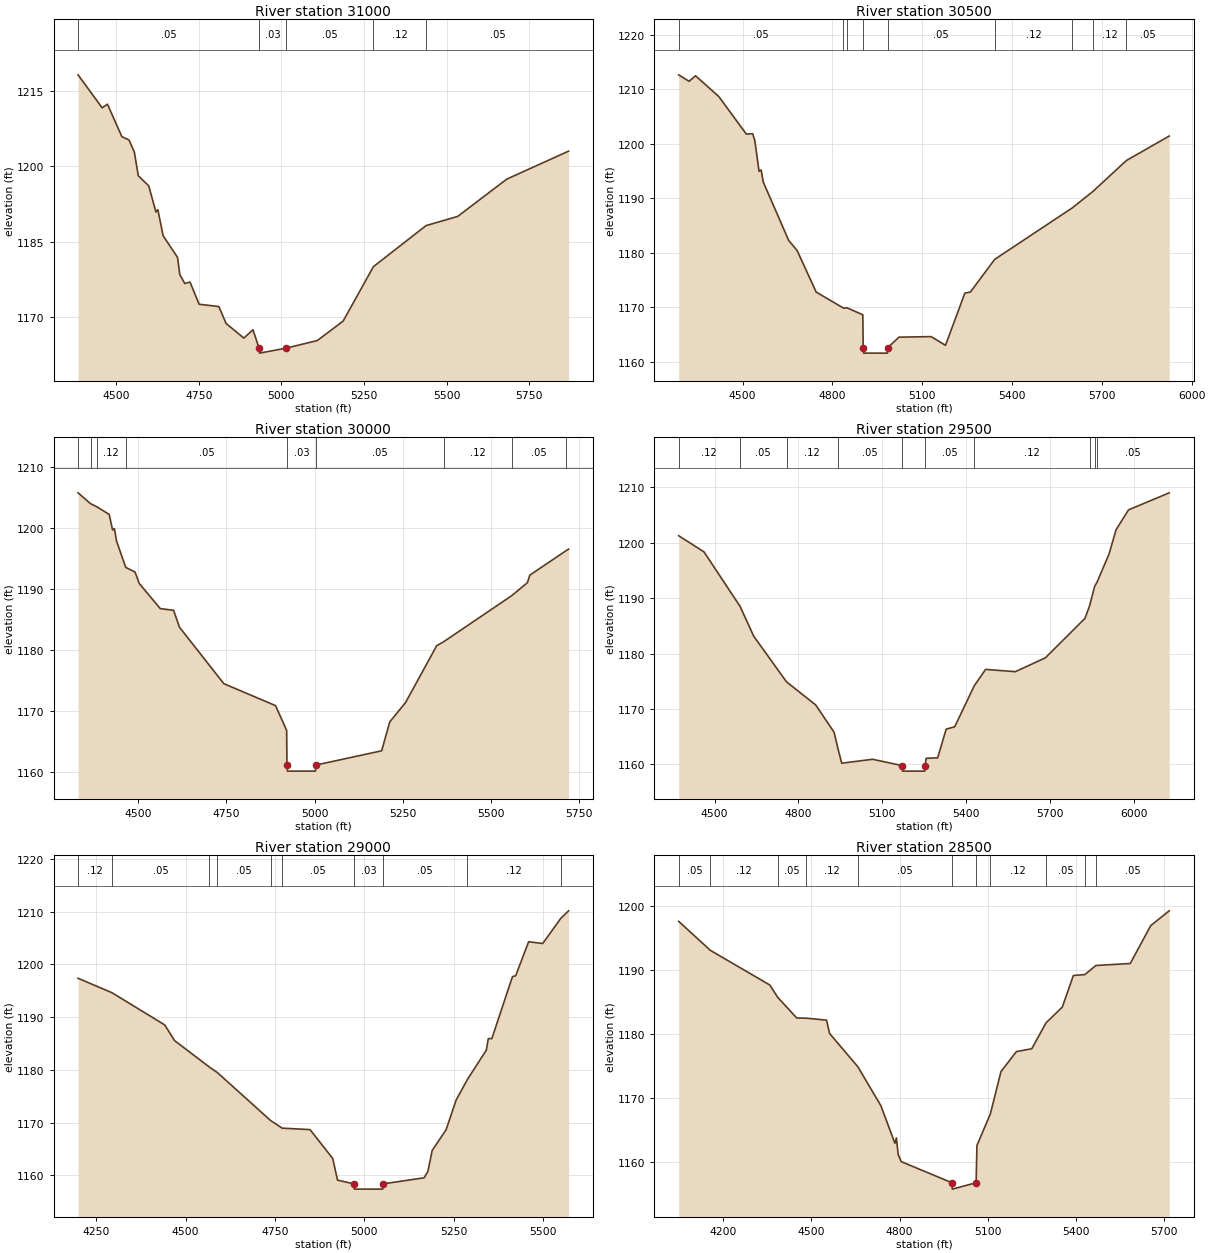
Type RM Length L Ch R = 1 ,31000   ,500,500,500
BEGIN DESCRIPTION:
HICKORY CREEK 62.0
END DESCRIPTION:
XS GIS Cut Line= 3
      2755576.04     10215422.82      2755872.67     10214883.86
      2756455.41     10214238.66
#Sta/Elev= 30
  4384.8 1218.29  4457.7  1211.7  4473.7 1212.43  4517.3 1205.95  4539.1 1205.28
  4555.2 1202.86  4567.1 1198.14  4598.7 1196.12  4620.5  1190.9  4626.2 1191.39
  4642.3 1186.16  4685.9 1181.83  4692.7 1178.42  4707.7 1176.64  4723.7 1176.91
  4751.2 1172.49  4810.9 1172.03  4832.7 1168.66  4886.6 1165.73  4914.1  1167.4
  4932.6 1163.73  4934.1 1162.73  5014.8 1163.73  5108.8 1165.24    5187 1169.12
  5278.7 1179.99    5438 1188.19  5533.7 1190.02  5682.4 1197.47  5869.4 1203.05
#Mann= 5 ,-1 , 0
  4384.8     .05       0  4932.6     .03       0  5014.8     .05       0
  5278.7     .12       0    5438     .05       0
Bank Sta=4932.6,5014.8
XS Rating Curve= 0 ,0
Exp/Cntr=0.3,0.1

Type RM Length L Ch R = 1 ,30500   ,500,500,500
BEGIN DESCRIPTION:
HICKORY CREEK 61.0
END DESCRIPTION:
XS GIS Cut Line= 3
      2755790.86     10215667.62      2756286.01     10215154.45
      2756535.32     10214263.68
#Sta/Elev= 30
  4286.9 1212.66  4321.7 1211.47    4343 1212.49  4420.7 1208.69  4512.8 1201.79
  4533.9 1201.86  4541.1 1200.62  4555.3 1194.96  4562.2 1195.22  4569.4 1192.99
  4654.3 1182.28  4682.3 1180.44  4746.1 1172.81  4837.2 1169.87  4849.2 1169.92
  4901.8 1168.64  4903.1 1162.61  4904.6 1161.61  4983.8 1161.61  4985.3 1162.61
  5022.4 1164.54  5129.9 1164.64  5177.9 1163.04  5242.7 1172.63    5261 1172.81
  5342.3 1178.81  5601.3 1188.25  5670.1 1191.26  5782.2 1196.95    5925 1201.43
#Mann= 9 ,-1 , 0
  4286.9     .05       0  4837.2     .12       0  4849.2     .05       0
  4903.1     .03       0  4985.3     .05       0  5342.3     .12       0
  5601.3     .05       0  5670.1     .12       0  5782.2     .05       0
Bank Sta=4903.1,4985.3
XS Rating Curve= 0 ,0
Exp/Cntr=0.3,0.1

Type RM Length L Ch R = 1 ,30000   ,500,500,500
BEGIN DESCRIPTION:
HICKORY CREEK 60.0
END DESCRIPTION:
XS GIS Cut Line= 3
      2756530.31     10216007.36      2756729.94     10215367.58
      2757029.95     10214713.29
#Sta/Elev= 30
  4329.8 1205.81  4365.2 1204.03  4382.7 1203.53  4418.1 1202.26  4427.5 1199.71
  4432.8 1199.94    4439 1197.86  4464.9 1193.56  4491.4 1192.79    4503 1190.93
  4562.8 1186.79  4600.5 1186.51  4617.1 1183.74  4742.8 1174.46  4889.5 1170.85
  4920.9 1166.78  4921.7 1161.09  4923.2 1160.09  5002.4 1160.09  5003.9 1161.09
  5190.1 1163.43  5213.1 1168.18  5257.9 1171.36    5346 1180.69  5365.9 1181.35
  5558.3  1188.9    5603 1191.04    5610 1192.29  5713.6 1196.34  5719.8 1196.56
#Mann= 9 ,-1 , 0
  4329.8     .12       0  4365.2     .05       0  4382.7     .12       0
  4464.9     .05       0  4921.7     .03       0  5003.9     .05       0
  5365.9     .12       0  5558.3     .05       0  5713.6     .12       0
Bank Sta=4921.7,5003.9
XS Rating Curve= 0 ,0
Exp/Cntr=0.3,0.1

Type RM Length L Ch R = 1 ,29500   ,500,500,500
BEGIN DESCRIPTION:
HICKORY CREEK 59.0
END DESCRIPTION:
XS GIS Cut Line= 3
      2756850.09     10216102.23      2757154.27     10215552.59
      2758212.33      10215163.6
#Sta/Elev= 30
  4371.8 1201.26  4462.2 1198.35  4591.3 1188.53  4640.4 1183.12  4757.8 1174.88
  4862.2 1170.71  4927.9  1165.8  4941.2 1162.96  4955.3  1160.2  5065.4 1160.91
  5171.4 1159.77  5172.9 1158.77  5252.3 1158.77  5253.8 1159.77  5257.2 1161.08
  5298.6 1161.17  5329.1 1166.35  5359.6 1166.77  5429.7 1174.18  5470.3 1177.13
  5576.8 1176.72  5684.1 1179.22  5825.8 1186.34  5842.1 1188.55  5860.2 1192.08
    5869 1192.87  5911.9 1197.94  5937.1 1202.33  5981.7 1205.92  6127.3    1209
#Mann= 10 ,-1 , 0
  4371.8     .12       0  4591.3     .05       0  4757.8     .12       0
  4941.2     .05       0  5171.4     .03       0  5253.8     .05       0
  5429.7     .12       0  5842.1     .05       0  5860.2     .12       0
    5869     .05       0
Bank Sta=5171.4,5253.8
XS Rating Curve= 0 ,0
Exp/Cntr=0.3,0.1

Type RM Length L Ch R = 1 ,29000   ,500,500,500
BEGIN DESCRIPTION:
HICKORY CREEK 58.0
END DESCRIPTION:
XS GIS Cut Line= 3
      2756954.96     10216252.16        2757585.     10215758.35
      2758098.71     10215507.91
#Sta/Elev= 30
  4199.5 1197.36  4294.2 1194.63  4441.8 1188.53  4469.5 1185.55    4567 1180.53
  4589.1  1179.5    4738 1170.41  4770.6 1168.96  4848.3 1168.69  4911.9 1163.21
  4925.2 1159.12  4970.7 1158.41  4972.2 1157.41  5051.6 1157.41  5053.1 1158.41
  5167.6 1159.56  5178.1  1160.8  5189.9 1164.73  5228.8 1168.65  5256.9 1174.27
  5288.1 1178.14  5341.5 1183.75    5347 1185.93  5356.8 1185.92  5414.6 1197.68
  5423.5 1197.83  5459.7 1204.28  5499.2 1203.95  5550.1 1208.75  5571.5 1210.14
#Mann= 10 ,-1 , 0
  4199.5     .12       0  4294.2     .05       0    4567     .12       0
  4589.1     .05       0    4738     .12       0  4770.6     .05       0
  4970.7     .03       0  5053.1     .05       0  5288.1     .12       0
  5550.1     .05       0
Bank Sta=4970.7,5053.1
XS Rating Curve= 0 ,0
Exp/Cntr=0.3,0.1

Type RM Length L Ch R = 1 ,28500   ,500,500,500
BEGIN DESCRIPTION:
HICKORY CREEK 57.0
END DESCRIPTION:
XS GIS Cut Line= 3
      2756890.08     10216362.05      2757826.78     10216189.85
      2758512.25     10216406.53
#Sta/Elev= 30
  4047.6 1197.64  4155.5  1193.1  4358.3 1187.67  4384.6 1185.77  4449.8 1182.51
  4482.4 1182.48  4551.5 1182.17  4561.7 1180.09  4658.3 1174.86  4736.3  1168.8
  4784.3 1162.89  4789.4 1163.72  4795.5 1161.14  4805.7 1160.02  4978.6 1156.71
  4980.1 1155.71    5061 1156.71  5063.8 1162.55  5109.6  1167.5  5145.7 1174.11
  5198.3 1177.25  5250.6 1177.69  5299.1 1181.74  5354.7 1184.22  5392.3 1189.16
  5431.6 1189.31  5469.2 1190.73  5586.2 1191.04  5656.1 1196.98  5718.9 1199.29
#Mann= 11 ,-1 , 0
  4047.6     .05       0  4155.5     .12       0  4384.6     .05       0
  4482.4     .12       0  4658.3     .05       0  4978.6     .05       0
    5061     .05       0  5109.6     .12       0  5299.1     .05       0
  5431.6     .12       0  5469.2     .05       0
Bank Sta=4978.6,5061
XS Rating Curve= 0 ,0
Exp/Cntr=0.3,0.1