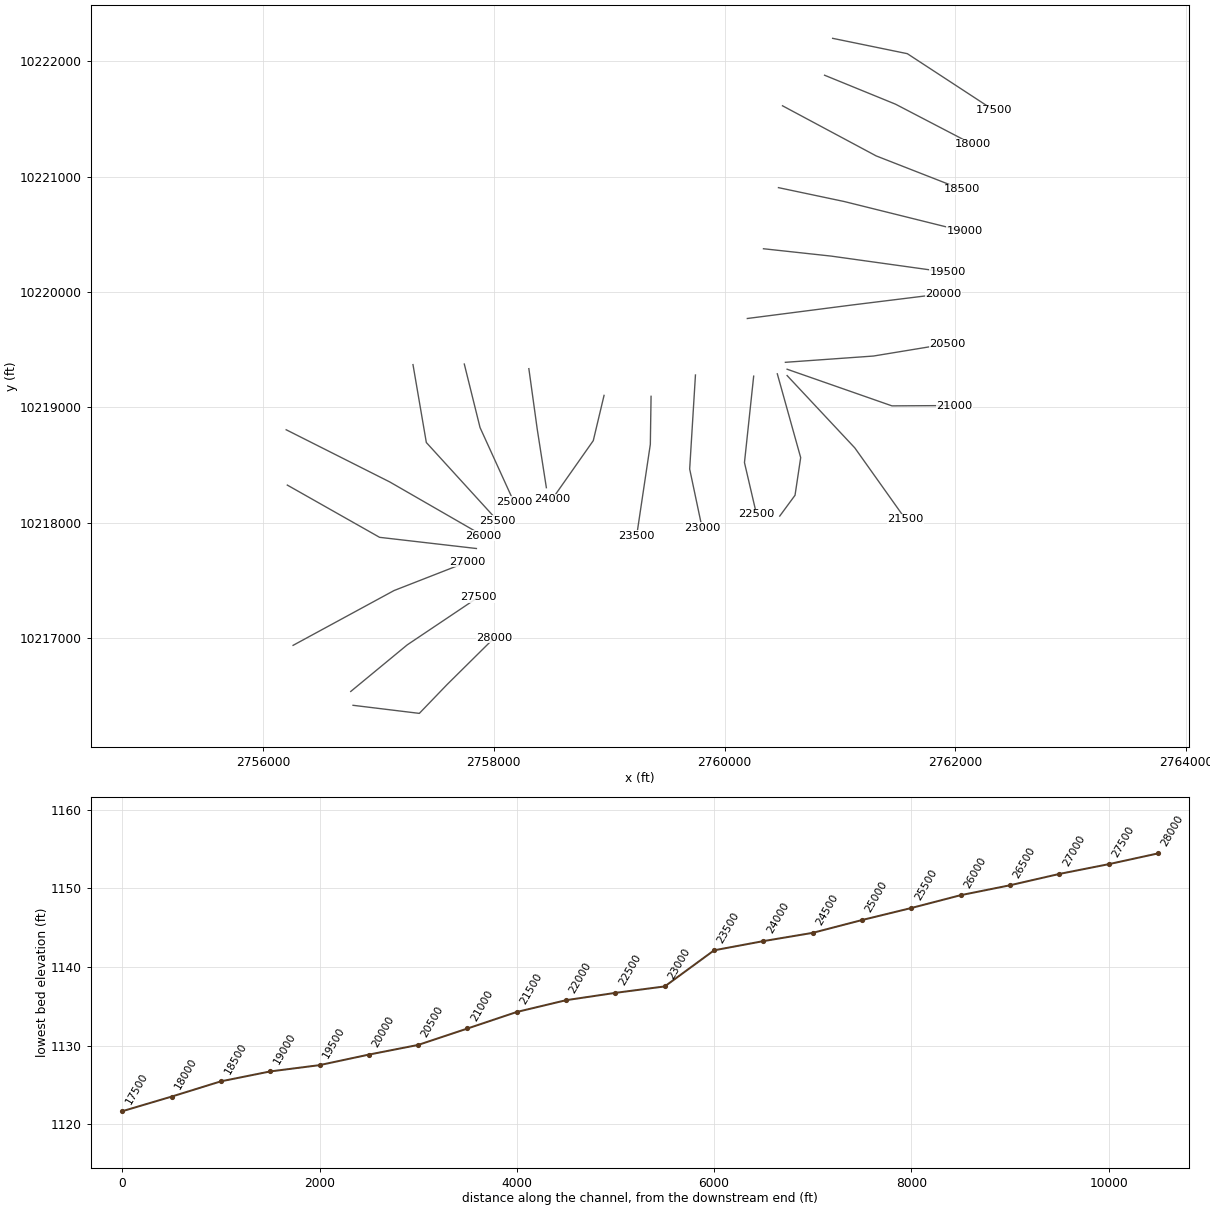
HEC-RAS study HICKORY CREEK.prj: HICKORY CREEK Base Level Engineering

--- HICKORY CREEK.g01 (geometry) --- (continued)

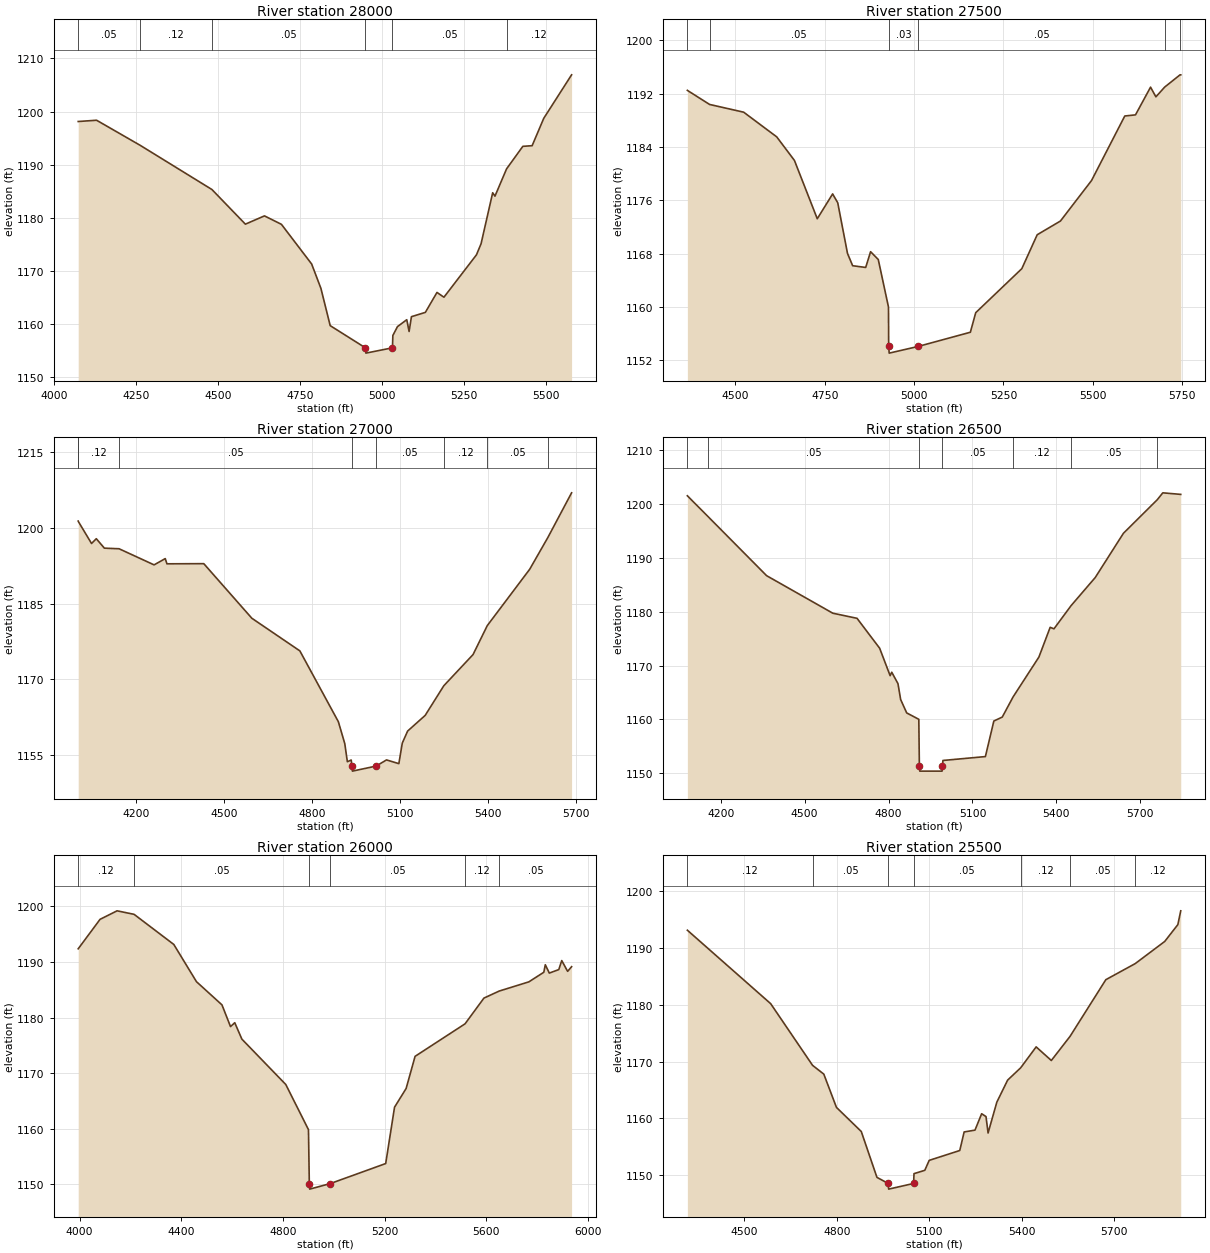
Type RM Length L Ch R = 1 ,28000   ,500,500,500
BEGIN DESCRIPTION:
HICKORY CREEK 56.0
END DESCRIPTION:
XS GIS Cut Line= 4
      2756780.13     10216417.01      2757354.68     10216347.07
      2757595.25     10216596.87      2758005.69     10217003.12
#Sta/Elev= 30
  4074.4 1198.12  4130.4 1198.36  4262.7 1193.65  4481.8  1185.3  4583.7 1178.77
  4641.8 1180.33  4693.5 1178.74  4785.6 1171.26  4813.9 1166.65  4842.1 1159.64
  4949.4 1155.46  4950.9 1154.46  5031.8 1155.46    5033 1157.79  5047.1 1159.46
  5075.4 1160.76  5082.5 1158.54  5089.6 1161.33    5132 1162.14  5167.4  1165.9
  5188.6    1165  5287.6 1172.98  5301.7 1175.07  5337.1 1184.69  5344.1 1184.05
  5379.4 1189.19    5429 1193.44  5457.3 1193.56  5492.7 1198.72  5577.5 1206.92
#Mann= 6 ,-1 , 0
  4074.4     .05       0  4262.7     .12       0  4481.8     .05       0
  4949.4     .05       0  5031.8     .05       0  5379.4     .12       0
Bank Sta=4949.4,5031.8
XS Rating Curve= 0 ,0
Exp/Cntr=0.3,0.1

Type RM Length L Ch R = 1 ,27500   ,500,500,500
BEGIN DESCRIPTION:
HICKORY CREEK 55.0
END DESCRIPTION:
XS GIS Cut Line= 3
      2756760.17     10216536.94       2757249.7     10216940.76
      2757869.27     10217356.28
#Sta/Elev= 30
  4365.4 1192.47  4427.6 1190.36    4523  1189.2  4615.5  1185.5    4665 1181.97
  4728.9 1173.23  4771.9 1176.95  4786.2 1175.62  4813.5 1168.03  4827.9 1166.19
  4864.4 1165.93  4878.1 1168.29  4899.6 1167.12  4928.2 1159.99  4928.7 1154.09
  4930.2 1153.09  5011.1 1154.09  5157.3 1156.22  5172.3 1159.15  5301.3 1165.75
  5344.3 1170.83  5409.4 1172.89  5496.4 1178.96  5589.4 1188.63  5619.4  1188.8
  5661.5 1192.95  5676.5  1191.5    5701 1192.96  5744.1  1194.8    5746  1194.8
#Mann= 6 ,-1 , 0
  4365.4     .12       0  4427.6     .05       0  4928.7     .03       0
  5011.1     .05       0    5701     .12       0  5744.1     .05       0
Bank Sta=4928.7,5011.1
XS Rating Curve= 0 ,0
Exp/Cntr=0.3,0.1

Type RM Length L Ch R = 1 ,27000   ,500,500,500
BEGIN DESCRIPTION:
HICKORY CREEK 54.0
END DESCRIPTION:
XS GIS Cut Line= 3
       2756260.5      10216936.6      2757135.58     10217411.62
      2757772.55     10217660.34
#Sta/Elev= 30
  4004.3 1201.34  4004.9 1201.24  4049.7  1196.9  4065.9 1197.85  4093.4 1195.98
  4143.4 1195.86  4262.6 1192.67  4300.6 1193.91  4306.3 1192.88  4431.8 1192.91
  4595.3 1182.11  4758.8 1175.65  4889.9 1161.63  4911.8 1157.28  4920.5 1153.71
  4933.6 1154.05  4936.2 1152.85  4937.7 1151.85  5018.6 1152.85  5053.8 1154.07
  5095.8 1153.33  5107.5  1157.4  5125.7 1159.78  5185.4 1162.88    5249 1168.76
  5348.4 1174.92  5396.8 1180.65  5541.2  1191.8  5602.9 1198.07  5683.8 1206.93
#Mann= 8 ,-1 , 0
  4004.3     .05       0  4004.9     .12       0  4143.4     .05       0
  4936.2     .05       0  5018.6     .05       0    5249     .12       0
  5396.8     .05       0  5602.9     .12       0
Bank Sta=4936.2,5018.6
XS Rating Curve= 0 ,0
Exp/Cntr=0.3,0.1

Type RM Length L Ch R = 1 ,26500   ,500,500,500
BEGIN DESCRIPTION:
HICKORY CREEK 53.0
END DESCRIPTION:
XS GIS Cut Line= 3
      2756210.55     10218325.55      2757010.31     10217872.84
      2757849.34     10217775.96
#Sta/Elev= 30
    4081 1201.53  4155.3 1197.65  4364.2  1186.7  4600.9 1179.73  4687.5 1178.78
  4768.3 1173.23  4805.8 1168.13  4811.6 1168.77  4833.8 1166.65  4843.4  1163.7
    4865 1161.22  4908.3 1160.03  4910.3 1151.41  4911.8 1150.41  4991.4 1150.41
  4992.9 1151.41  4994.6 1152.39  5146.3 1153.11  5176.5 1159.71  5206.7 1160.45
  5245.2 1164.18  5337.6 1171.59  5377.9 1177.11  5391.4 1176.83    5453 1181.16
  5538.9 1186.35  5639.6 1194.56  5760.5 1200.79  5780.5 1202.08  5844.6 1201.79
#Mann= 7 ,-1 , 0
    4081     .12       0  4155.3     .05       0  4910.3     .03       0
  4992.9     .05       0  5245.2     .12       0    5453     .05       0
  5760.5     .12       0
Bank Sta=4910.3,4992.9
XS Rating Curve= 0 ,0
Exp/Cntr=0.3,0.1

Type RM Length L Ch R = 1 ,26000   ,500,500,500
BEGIN DESCRIPTION:
HICKORY CREEK 52.0
END DESCRIPTION:
XS GIS Cut Line= 3
      2756200.59     10218805.16      2757098.22     10218352.96
      2757909.24     10217885.89
#Sta/Elev= 30
  3994.9 1192.39  4080.9 1197.69  4147.8 1199.22  4214.7 1198.59    4371 1193.17
  4460.2 1186.47  4560.5  1182.3  4594.1 1178.39  4610.8 1179.09  4638.8 1176.14
  4811.6 1167.97  4900.8 1159.85  4904.1 1150.15  4905.6 1149.15  4986.7 1150.15
  5204.6 1153.75  5239.4 1163.89    5285 1167.26  5320.2 1173.04  5516.8 1178.89
  5591.1 1183.52  5650.8 1184.78  5767.8 1186.44  5826.7 1188.17  5832.5 1189.52
  5848.3 1188.02  5885.6 1188.65  5897.2 1190.27  5920.3 1188.33  5935.9 1189.17
#Mann= 6 ,-1 , 0
  3994.9     .12       0  4214.7     .05       0  4904.1     .03       0
  4986.7     .05       0  5516.8     .12       0  5650.8     .05       0
Bank Sta=4904.1,4986.7
XS Rating Curve= 0 ,0
Exp/Cntr=0.3,0.1

Type RM Length L Ch R = 1 ,25500   ,500,500,500
BEGIN DESCRIPTION:
HICKORY CREEK 51.0
END DESCRIPTION:
XS GIS Cut Line= 3
      2757299.72     10219369.74      2757415.39     10218694.48
      2758033.13     10218016.91
#Sta/Elev= 30
  4314.9 1193.17  4585.4 1180.22  4721.5 1169.34  4757.9  1167.8    4799 1161.93
  4879.6 1157.68  4930.4  1149.6  4966.9 1148.52  4968.4 1147.52  5049.5 1148.52
  5050.8 1150.25  5085.9 1150.84  5100.1 1152.59  5199.4 1154.33  5213.6  1157.6
  5248.8 1157.92  5270.4 1160.81  5284.6 1160.31  5291.3 1157.42  5319.7 1162.85
  5354.8 1166.74  5397.3 1168.92  5447.4  1172.6  5496.7  1170.2  5557.4 1174.45
  5673.7 1184.45    5769 1187.28  5864.9 1191.19  5907.5 1194.16  5916.9 1196.59
#Mann= 7 ,-1 , 0
  4314.9     .12       0  4721.5     .05       0  4966.9     .03       0
  5049.5     .05       0  5397.3     .12       0  5557.4     .05       0
    5769     .12       0
Bank Sta=4966.9,5049.5
XS Rating Curve= 0 ,0
Exp/Cntr=0.3,0.1

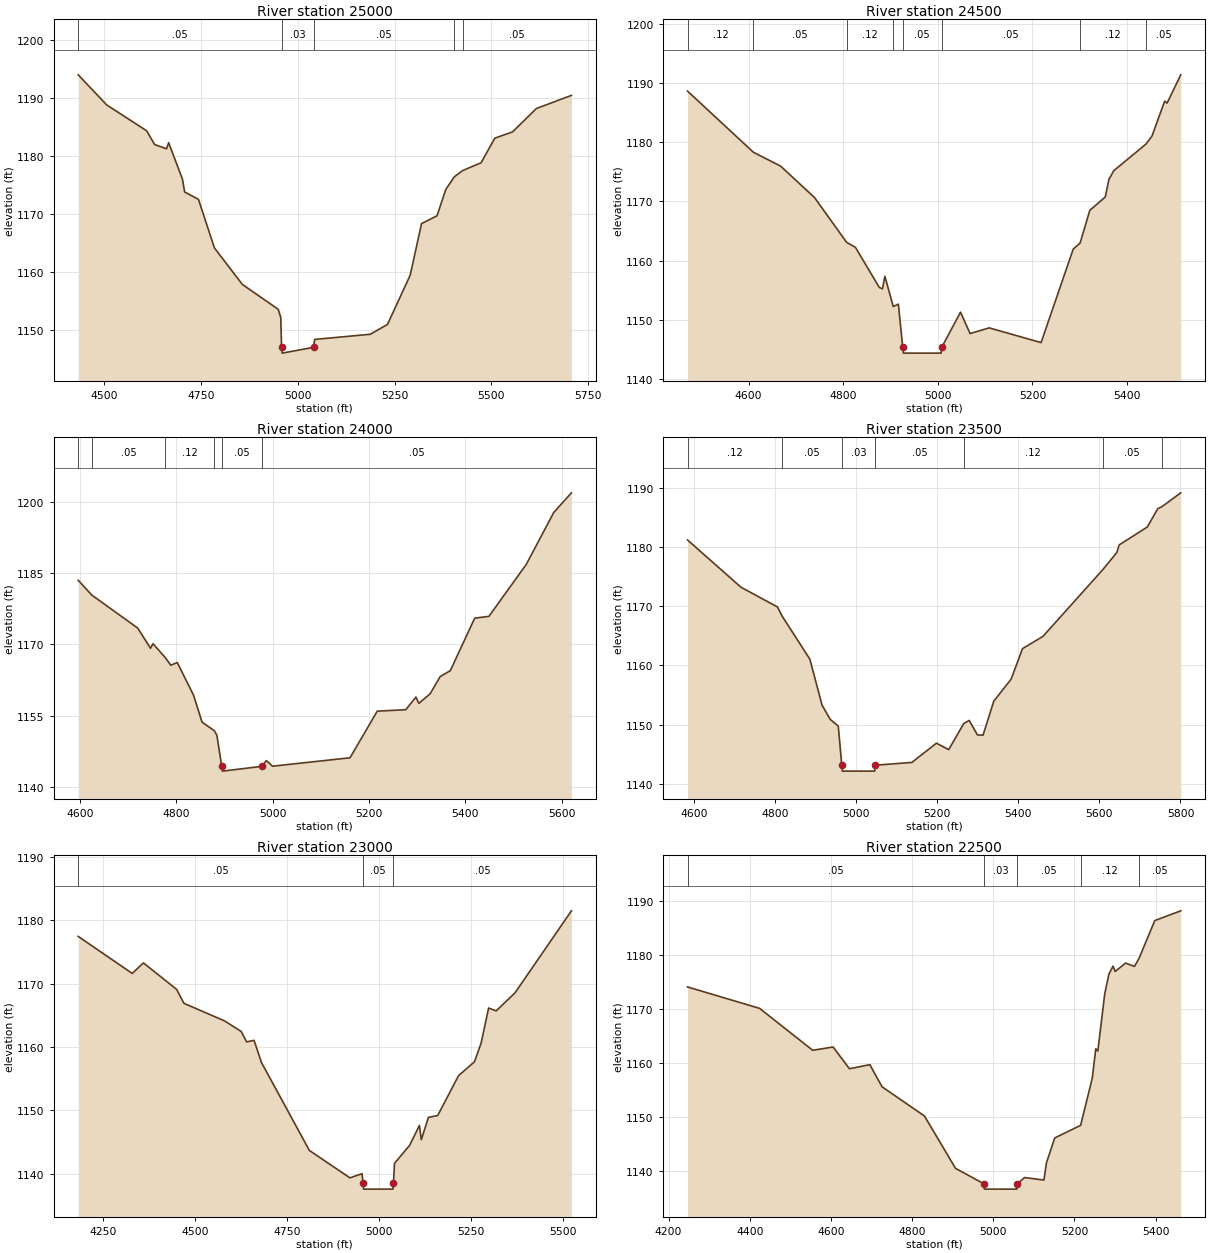
Type RM Length L Ch R = 1 ,25000   ,500,500,500
BEGIN DESCRIPTION:
HICKORY CREEK 50.0
END DESCRIPTION:
XS GIS Cut Line= 3
      2757744.39     10219374.69      2757880.92     10218824.16
      2758174.04     10218180.68
#Sta/Elev= 30
  4432.8 1193.96  4506.5 1188.77  4609.6 1184.32  4630.2 1181.95  4661.1 1181.21
  4666.5 1182.27  4702.3 1175.94  4707.8 1173.77  4743.5  1172.5  4784.7 1164.13
  4856.8 1157.84  4949.6 1153.54  4956.1 1152.15  4958.2 1146.99  4959.7 1145.99
  5040.8 1146.99  5043.6 1148.35  5187.4 1149.24  5231.9 1150.94  5290.6 1159.43
  5319.8 1168.31  5359.8 1169.66  5382.8 1174.24  5404.7 1176.39  5426.4 1177.47
  5473.7  1178.8  5509.1 1183.04  5555.2 1184.13  5616.5 1188.15  5707.1 1190.42
#Mann= 5 ,-1 , 0
  4432.8     .05       0  4958.2     .03       0  5040.8     .05       0
  5404.7     .12       0  5426.4     .05       0
Bank Sta=4958.2,5040.8
XS Rating Curve= 0 ,0
Exp/Cntr=0.3,0.1

Type RM Length L Ch R = 1 ,24500   ,500,500,500
BEGIN DESCRIPTION:
HICKORY CREEK 49.0
END DESCRIPTION:
XS GIS Cut Line= 3
      2758303.96     10219334.73      2758376.49     10218810.62
      2758455.69     10218303.06
#Sta/Elev= 30
  4470.9 1188.67  4610.1 1178.33  4667.6 1175.99  4739.4 1170.67  4807.3 1163.09
  4825.9 1162.25  4876.3 1155.47  4883.1 1155.24  4888.1 1157.36  4905.9 1152.24
  4916.7 1152.64  4925.9 1145.36  4927.4 1144.36    5007 1144.36  5008.5 1145.36
  5048.1 1151.29  5068.3 1147.67  5108.8 1148.63  5218.4 1146.14  5286.3 1161.94
  5300.9 1162.98  5321.4  1168.5  5354.1 1170.76  5361.8 1173.73    5372  1175.2
  5440.2 1179.71  5452.9 1181.07  5479.7 1186.97  5484.8 1186.63  5513.7 1191.42
#Mann= 8 ,-1 , 0
  4470.9     .12       0  4610.1     .05       0  4807.3     .12       0
  4905.9     .05       0  4925.9     .05       0  5008.5     .05       0
  5300.9     .12       0  5440.2     .05       0
Bank Sta=4925.9,5008.5
XS Rating Curve= 0 ,0
Exp/Cntr=0.3,0.1

Type RM Length L Ch R = 1 ,24000   ,500,500,500
BEGIN DESCRIPTION:
HICKORY CREEK 48.0
END DESCRIPTION:
XS GIS Cut Line= 3
      2758955.69     10219103.13      2758862.29     10218710.79
      2758505.69     10218203.12
#Sta/Elev= 30
  4596.7 1183.52  4624.7 1180.41  4720.1 1173.45  4746.8 1169.19  4751.9 1170.15
  4777.1 1167.26    4789 1165.61  4802.3 1166.19  4836.2 1159.29  4853.7 1153.64
  4879.2 1151.82  4884.5 1150.88  4894.6 1144.31  4896.1 1143.31  4977.3 1144.31
  4987.3 1145.53    5000 1144.35  5160.8 1146.12  5217.4 1155.94  5276.6 1156.25
  5297.6 1158.91  5303.7 1157.58  5327.1  1159.6  5348.1 1163.24    5369 1164.47
  5419.6 1175.52  5449.2 1175.92  5526.7 1186.86  5583.7 1197.79  5620.4 1201.93
#Mann= 6 ,-1 , 0
  4596.7     .12       0  4624.7     .05       0  4777.1     .12       0
  4879.2     .05       0  4894.6     .05       0  4977.3     .05       0
Bank Sta=4894.6,4977.3
XS Rating Curve= 0 ,0
Exp/Cntr=0.3,0.1

Type RM Length L Ch R = 1 ,23500   ,500,500,500
BEGIN DESCRIPTION:
HICKORY CREEK 47.0
END DESCRIPTION:
XS GIS Cut Line= 3
      2759363.13     10219094.98      2759356.76     10218678.93
       2759238.4     10217887.02
#Sta/Elev= 30
  4583.9 1181.17  4715.8 1173.19  4805.8 1169.86  4817.2 1168.33  4885.8 1161.03
  4915.8 1153.28  4935.8 1150.89  4955.8 1149.75  4964.5 1143.14    4966 1142.14
  5045.7 1142.14  5047.2 1143.14  5137.3 1143.61    5198 1146.86  5228.3 1145.77
  5265.5 1150.19  5278.9  1150.7  5299.1 1148.25    5313 1148.22  5339.5 1153.96
  5382.2 1157.66  5410.3 1162.82  5460.9  1164.9  5608.4 1176.16  5642.9 1179.05
  5648.9 1180.34  5718.2 1183.36    5744 1186.45  5753.4 1186.75  5800.7 1189.13
#Mann= 7 ,-1 , 0
  4583.9     .12       0  4817.2     .05       0  4964.5     .03       0
  5047.2     .05       0  5265.5     .12       0  5608.4     .05       0
  5753.4     .12       0
Bank Sta=4964.5,5047.2
XS Rating Curve= 0 ,0
Exp/Cntr=0.3,0.1

Type RM Length L Ch R = 1 ,23000   ,500,500,500
BEGIN DESCRIPTION:
HICKORY CREEK 46.0
END DESCRIPTION:
XS GIS Cut Line= 3
      2759747.83     10219279.77      2759697.74     10218464.71
      2759805.69     10217953.07
#Sta/Elev= 30
  4183.4 1177.46  4330.3 1171.61  4360.4 1173.28  4450.6  1169.1  4470.6 1166.89
  4580.8 1164.12  4625.9 1162.46  4640.9  1160.8    4661 1161.05    4681 1157.56
  4811.2 1143.66  4921.4 1139.33  4954.2 1139.99  4956.9 1138.55  4958.4 1137.55
  5038.1 1137.55  5039.6 1138.55  5042.5 1141.63  5083.4 1144.46  5110.1 1147.61
  5115.2 1145.36  5134.5 1148.88  5159.8 1149.18  5216.3 1155.47  5259.4 1157.65
  5277.6  1160.6    5298 1166.15  5318.5  1165.7  5369.6 1168.54  5522.9  1181.5
#Mann= 3 ,-1 , 0
  4183.4     .05       0  4956.9     .05       0  5039.6     .05       0
Bank Sta=4956.9,5039.6
XS Rating Curve= 0 ,0
Exp/Cntr=0.3,0.1

Type RM Length L Ch R = 1 ,22500   ,500,500,500
BEGIN DESCRIPTION:
HICKORY CREEK 45.0
END DESCRIPTION:
XS GIS Cut Line= 3
      2760252.44     10219269.76      2760172.59     10218520.61
      2760277.42     10218070.76
#Sta/Elev= 30
  4246.6  1174.1  4424.3 1170.14    4555 1162.39  4605.3    1163  4645.6 1158.98
  4695.8 1159.74    4726 1155.64  4830.4 1150.25    4907 1140.57  4976.6 1137.73
  4978.1 1136.73  5057.8 1136.73  5059.3 1137.73  5077.1 1138.87  5124.8 1138.41
  5130.9 1141.56  5151.4 1146.19  5215.2 1148.52  5243.9 1157.24  5252.5 1162.67
  5257.6 1162.27  5274.7 1172.87  5284.9 1176.47  5295.1 1177.95  5300.2 1176.96
    5326 1178.51  5347.9  1177.9  5358.8 1179.33  5397.9 1186.37  5461.9 1188.17
#Mann= 5 ,-1 , 0
  4246.6     .05       0  4976.6     .03       0  5059.3     .05       0
  5215.2     .12       0  5358.8     .05       0
Bank Sta=4976.6,5059.3
XS Rating Curve= 0 ,0
Exp/Cntr=0.3,0.1

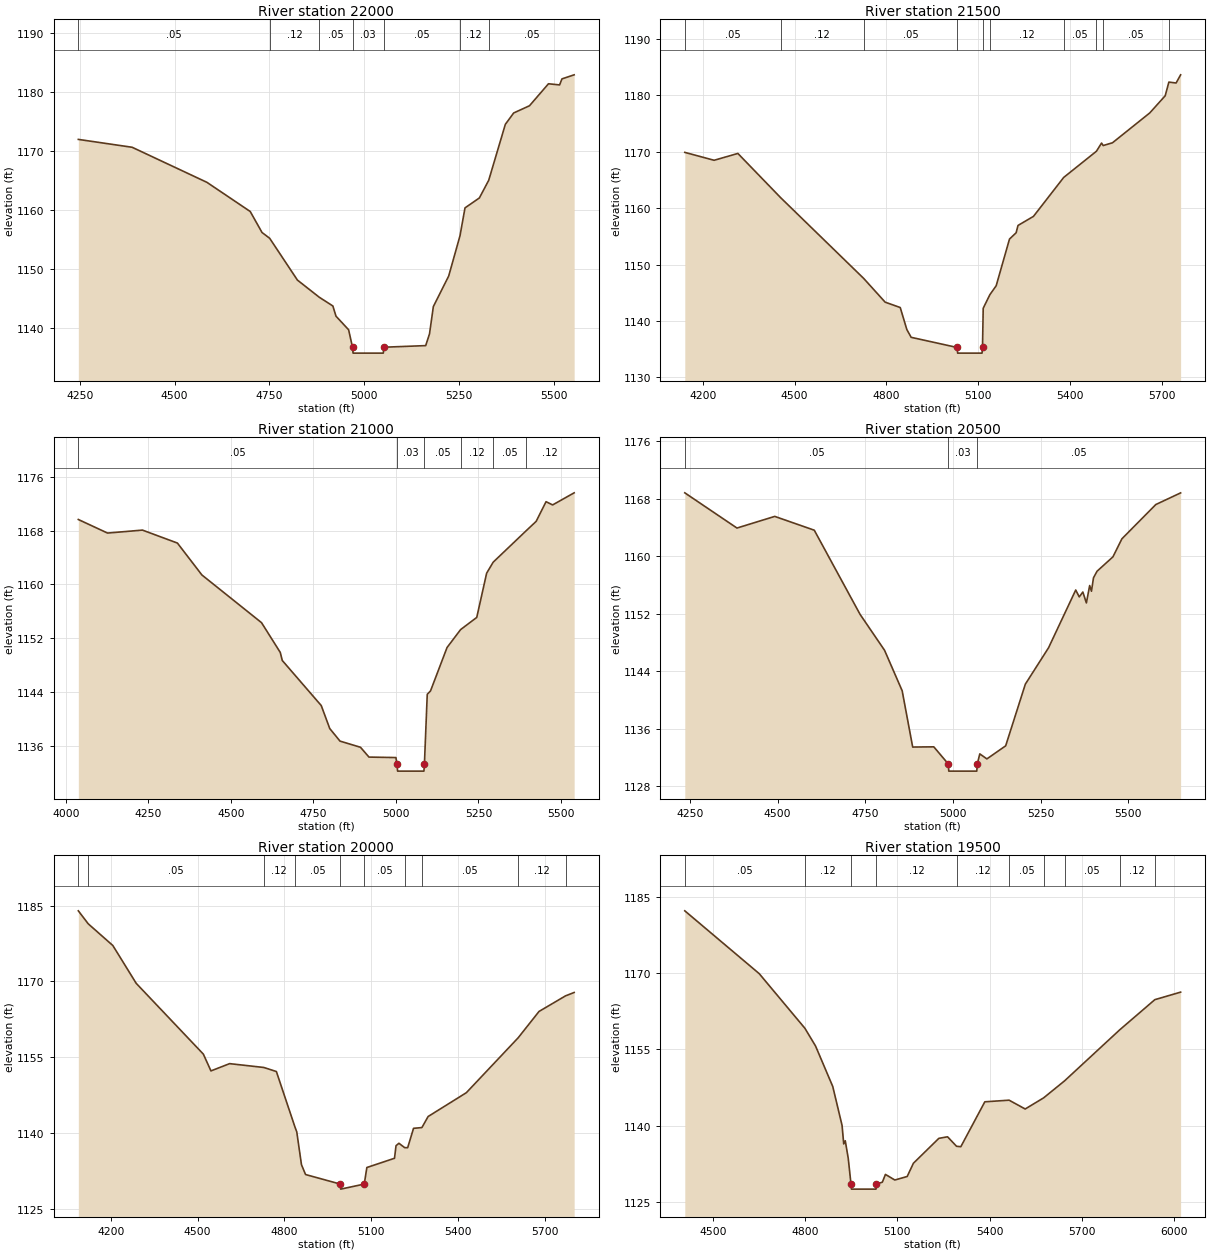
Type RM Length L Ch R = 1 ,22000   ,500,500,500
BEGIN DESCRIPTION:
HICKORY CREEK 44.0
END DESCRIPTION:
XS GIS Cut Line= 4
      2760457.28     10219289.81      2760659.82     10218563.62
      2760610.82     10218237.31      2760478.14     10218056.92
#Sta/Elev= 30
  4246.1 1171.94    4388 1170.61  4585.3 1164.68  4699.5 1159.75  4730.6  1156.2
  4750.8 1155.22    4824 1148.15  4881.4 1145.26  4917.5 1143.77  4925.7 1142.05
    4959 1139.75  4969.3  1136.8  4970.8  1135.8  5050.5  1135.8    5052  1136.8
  5162.3 1137.07  5172.4 1139.06  5182.5 1143.67    5223 1148.84  5252.8 1155.65
    5266 1160.36  5303.9 1162.04  5328.5 1165.02  5372.4 1174.49  5394.4 1176.41
  5436.1 1177.63  5486.2 1181.35  5515.5 1181.15  5521.7 1182.17  5553.9 1182.86
#Mann= 7 ,-1 , 0
  4246.1     .05       0  4750.8     .12       0  4881.4     .05       0
  4969.3     .03       0    5052     .05       0  5252.8     .12       0
  5328.5     .05       0
Bank Sta=4969.3,5052
XS Rating Curve= 0 ,0
Exp/Cntr=0.3,0.1

Type RM Length L Ch R = 1 ,21500   ,500,500,500
BEGIN DESCRIPTION:
HICKORY CREEK 43.0
END DESCRIPTION:
XS GIS Cut Line= 3
      2760542.22     10219274.81      2761129.02     10218647.88
      2761570.22     10218027.47
#Sta/Elev= 30
  4141.3 1169.87  4237.1 1168.47  4314.7 1169.68  4455.1 1161.81  4725.7 1147.54
  4795.9 1143.33  4845.2 1142.38  4866.7 1138.49  4880.9  1137.1  5031.2  1135.3
  5032.7  1134.3  5112.5  1134.3    5114  1135.3  5116.3 1142.25  5137.9 1144.64
  5158.7 1146.24  5202.2 1154.51  5223.9 1155.63    5230 1156.92  5280.5 1158.53
  5379.3 1165.43  5486.2 1170.07    5503 1171.52  5508.3 1171.08  5538.7 1171.57
  5660.5 1176.86  5710.9  1179.9  5722.9 1182.32  5746.5 1182.16  5761.3 1183.61
#Mann= 10 ,-1 , 0
  4141.3     .05       0  4455.1     .12       0  4725.7     .05       0
  5031.2     .03       0    5114     .05       0  5137.9     .12       0
  5379.3     .05       0  5486.2     .12       0  5508.3     .05       0
  5722.9     .12       0
Bank Sta=5031.2,5114
XS Rating Curve= 0 ,0
Exp/Cntr=0.3,0.1

Type RM Length L Ch R = 1 ,21000   ,500,500,500
BEGIN DESCRIPTION:
HICKORY CREEK 42.0
END DESCRIPTION:
XS GIS Cut Line= 3
      2760542.18     10219329.78      2761450.78      10219012.2
      2761990.88       10219015.
#Sta/Elev= 30
  4037.5 1169.66    4126 1167.64  4231.9 1168.08  4337.8 1166.15    4412  1161.4
  4592.7  1154.3  4649.5 1149.87  4655.6 1148.67  4773.7 1141.96  4799.4 1138.54
  4830.5 1136.67  4892.6 1135.75  4918.3 1134.29  4999.9 1134.22  5003.5  1133.2
    5005  1132.2  5084.8  1132.2  5086.3  1133.2  5094.9 1143.63  5104.9 1144.15
  5154.9  1150.6    5196 1153.27  5244.9 1155.08  5274.9 1161.67  5294.8 1163.31
  5393.5 1167.93  5424.9 1169.38  5454.9 1172.31  5474.9 1171.83  5540.1 1173.63
#Mann= 6 ,-1 , 0
  4037.5     .05       0  5003.5     .03       0  5086.3     .05       0
    5196     .12       0  5294.8     .05       0  5393.5     .12       0
Bank Sta=5003.5,5086.3
XS Rating Curve= 0 ,0
Exp/Cntr=0.3,0.1

Type RM Length L Ch R = 1 ,20500   ,500,500,500
BEGIN DESCRIPTION:
HICKORY CREEK 41.0
END DESCRIPTION:
XS GIS Cut Line= 3
      2760527.28     10219389.72      2761290.25     10219444.02
      2761930.92     10219549.55
#Sta/Elev= 30
  4235.1 1168.83  4383.9 1163.93  4491.7 1165.55  4604.4 1163.63  4734.8 1151.94
  4804.9 1146.92  4855.1 1141.29  4885.1 1133.46  4945.3 1133.49  4986.6 1131.11
  4988.1 1130.11  5067.9 1130.11  5069.4 1131.11  5076.5 1132.51  5096.7 1131.81
  5150.3 1133.63  5206.4 1142.21  5272.7 1147.28  5350.1 1155.31  5360.2 1154.35
  5370.4 1155.03  5380.5 1153.51  5389.9 1155.93    5395 1155.14  5400.8 1157.01
  5410.9 1157.92  5456.2 1159.92  5481.8 1162.43  5578.5  1167.2  5649.3 1168.82
#Mann= 3 ,-1 , 0
  4235.1     .05       0  4986.6     .03       0  5069.4     .05       0
Bank Sta=4986.6,5069.4
XS Rating Curve= 0 ,0
Exp/Cntr=0.3,0.1

Type RM Length L Ch R = 1 ,20000   ,500,500,500
BEGIN DESCRIPTION:
HICKORY CREEK 40.0
END DESCRIPTION:
XS GIS Cut Line= 3
      2760197.44     10219769.42      2761101.65     10219886.01
       2761896.2     10219984.26
#Sta/Elev= 30
  4088.3 1183.99  4122.3 1181.43  4207.5 1177.12  4288.2 1169.63  4520.1 1155.61
  4546.3 1152.29  4610.8 1153.73  4728.8 1152.97  4772.2 1152.17  4836.3  1141.2
  4842.7  1140.2  4858.9 1133.72    4873 1131.77  4992.9 1129.88  4994.4 1128.88
  5075.7 1129.88  5084.7 1133.16  5180.2 1134.99  5185.4 1137.48  5195.5 1137.96
  5215.4 1137.09  5225.7 1137.09  5245.9 1140.92  5274.8 1141.07  5296.3 1143.26
  5428.4 1147.98  5607.3 1158.85  5679.2 1164.06  5770.8 1167.15  5800.6 1167.82
#Mann= 10 ,-1 , 0
  4088.3     .12       0  4122.3     .05       0  4728.8     .12       0
  4836.3     .05       0  4992.9     .05       0  5075.7     .05       0
  5215.4     .12       0  5274.8     .05       0  5607.3     .12       0
  5770.8     .05       0
Bank Sta=4992.9,5075.7
XS Rating Curve= 0 ,0
Exp/Cntr=0.3,0.1

Type RM Length L Ch R = 1 ,19500   ,500,500,500
BEGIN DESCRIPTION:
HICKORY CREEK 39.0
END DESCRIPTION:
XS GIS Cut Line= 3
      2760337.39     10220373.96      2760924.63     10220310.15
      2761936.15     10220169.11
#Sta/Elev= 30
  4409.3  1182.2  4651.3 1169.86  4799.8 1159.13  4834.4 1155.65  4890.4 1147.69
  4920.6 1140.05    4926 1136.41    4931 1137.04  4940.7 1133.58  4949.6 1128.54
  4951.1 1127.54  5030.9 1127.54  5032.4 1128.54  5051.5  1128.9  5061.6 1130.43
  5092.1 1129.33  5132.3 1130.02  5152.5 1132.62  5235.2 1137.51  5263.6 1137.82
  5292.7 1135.96  5306.7 1135.87  5384.7 1144.69  5463.6 1145.01    5516 1143.28
    5576 1145.47  5643.9  1148.8    5823 1158.81  5937.4 1164.75  6021.3 1166.23
#Mann= 10 ,-1 , 0
  4409.3     .05       0  4799.8     .12       0  4949.6     .03       0
  5032.4     .12       0  5292.7     .12       0  5463.6     .05       0
    5576     .12       0  5643.9     .05       0    5823     .12       0
  5937.4     .05       0
Bank Sta=4949.6,5032.4
XS Rating Curve= 0 ,0
Exp/Cntr=0.3,0.1

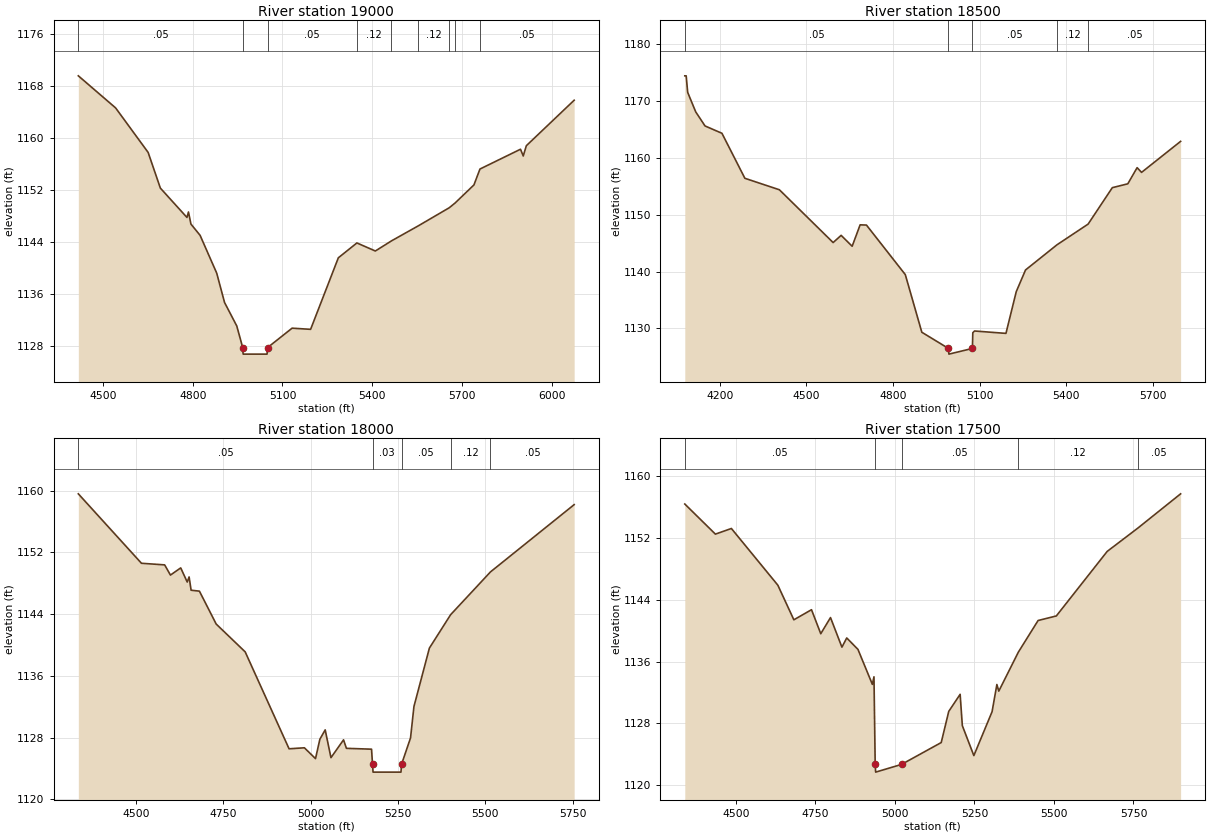
Type RM Length L Ch R = 1 ,19000   ,500,500,500
BEGIN DESCRIPTION:
HICKORY CREEK 38.0
END DESCRIPTION:
XS GIS Cut Line= 3
      2760467.31     10220903.54      2761037.34     10220783.19
       2762080.9     10220523.87
#Sta/Elev= 30
  4417.4 1169.62    4542 1164.68  4650.8 1157.82  4691.7 1152.32  4780.6  1147.8
  4785.7 1148.64  4793.9 1146.78  4824.6 1145.04  4880.1 1139.22  4906.3  1134.7
  4947.2 1131.08  4967.1 1127.74  4968.6 1126.74  5048.5 1126.74    5050 1127.74
  5132.2 1130.74  5194.1 1130.56  5286.8 1141.58  5348.9 1143.87  5410.5 1142.63
  5464.5 1144.19  5554.7 1146.52  5657.5 1149.29  5676.8 1150.01  5740.2 1152.81
  5760.4 1155.26  5895.9 1158.31  5905.1 1157.27  5915.4 1158.85  6075.3 1165.86
#Mann= 9 ,-1 , 0
  4417.4     .05       0  4967.1     .03       0    5050     .05       0
  5348.9     .12       0  5464.5     .05       0  5554.7     .12       0
  5657.5     .05       0  5676.8     .12       0  5760.4     .05       0
Bank Sta=4967.1,5050
XS Rating Curve= 0 ,0
Exp/Cntr=0.3,0.1

Type RM Length L Ch R = 1 ,18500   ,500,500,500
BEGIN DESCRIPTION:
HICKORY CREEK 37.0
END DESCRIPTION:
XS GIS Cut Line= 3
      2760502.24     10221613.01      2761314.29      10221178.5
      2762056.04     10220888.56
#Sta/Elev= 30
    4079 1174.45  4083.8 1174.45    4089 1171.54  4116.9  1168.1  4149.1 1165.63
  4207.7 1164.34  4287.1 1156.42  4406.7  1154.4  4592.8 1145.11  4620.5 1146.38
  4658.7 1144.46  4686.3 1148.23  4708.2 1148.19  4842.8 1139.47    4900 1129.33
  4992.3 1126.48  4993.8 1125.48  5075.2 1126.48  5076.6 1129.25  5082.7 1129.55
  5191.4 1129.13    5227 1136.46  5259.2 1140.29  5368.2 1144.72    5476 1148.36
  5559.8 1154.77  5613.5 1155.45  5645.7 1158.29  5661.1 1157.46  5796.4 1162.92
#Mann= 5 ,-1 , 0
    4079     .05       0  4992.3     .03       0  5075.2     .05       0
  5368.2     .12       0    5476     .05       0
Bank Sta=4992.3,5075.2
XS Rating Curve= 0 ,0
Exp/Cntr=0.3,0.1

Type RM Length L Ch R = 1 ,18000   ,500,500,500
BEGIN DESCRIPTION:
HICKORY CREEK 36.0
END DESCRIPTION:
XS GIS Cut Line= 3
      2760866.98     10221877.79      2761481.91     10221626.75
      2762150.82     10221278.34
#Sta/Elev= 30
  4335.8 1159.57  4516.4 1150.58  4582.8 1150.37  4599.3 1149.05  4628.7 1149.98
  4647.3 1148.15  4652.7 1148.81  4658.4 1147.09  4682.2 1146.97  4730.2 1142.71
  4813.1 1139.11  4938.7 1126.56  4982.5 1126.69  5014.3 1125.29  5026.8  1127.8
    5042 1129.01  5058.5 1125.41  5094.5 1127.72  5102.7 1126.62  5174.6 1126.51
  5177.4 1124.54  5178.9 1123.54  5258.8 1123.54  5260.3 1124.54  5286.1 1127.96
  5295.9 1132.04  5340.1  1139.6  5400.8 1143.92  5514.8 1149.46  5754.2 1158.17
#Mann= 5 ,-1 , 0
  4335.8     .05       0  5177.4     .03       0  5260.3     .05       0
  5400.8     .12       0  5514.8     .05       0
Bank Sta=5177.4,5260.3
XS Rating Curve= 0 ,0
Exp/Cntr=0.3,0.1

Type RM Length L Ch R = 1 ,17500   ,500,500,500
BEGIN DESCRIPTION:
HICKORY CREEK 35.0
END DESCRIPTION:
XS GIS Cut Line= 3
      2760936.92     10222197.55      2761584.01     10222064.62
      2762335.85     10221573.02
#Sta/Elev= 30
  4339.4 1156.41  4435.6 1152.51  4485.9 1153.24  4631.9  1145.9  4682.3 1141.41
  4737.8 1142.72  4766.9 1139.61  4797.5  1141.7  4833.4 1137.87  4848.6 1139.06
  4883.8 1137.58  4929.1 1133.05  4934.2 1134.03    4938 1122.68  4939.5 1121.68
  5020.9 1122.68  5145.6 1125.51  5169.3 1129.55  5205.1 1131.76    5212  1127.7
  5248.2 1123.82  5305.5 1129.51  5320.6 1133.03  5326.6 1132.17  5388.1 1137.22
  5450.2 1141.32  5507.5 1141.91  5667.4 1150.27  5764.1  1153.3  5898.3 1157.73
#Mann= 5 ,-1 , 0
  4339.4     .05       0    4938     .03       0  5020.9     .05       0
  5388.1     .12       0  5764.1     .05       0
Bank Sta=4938,5020.9
XS Rating Curve= 0 ,0
Exp/Cntr=0.3,0.1