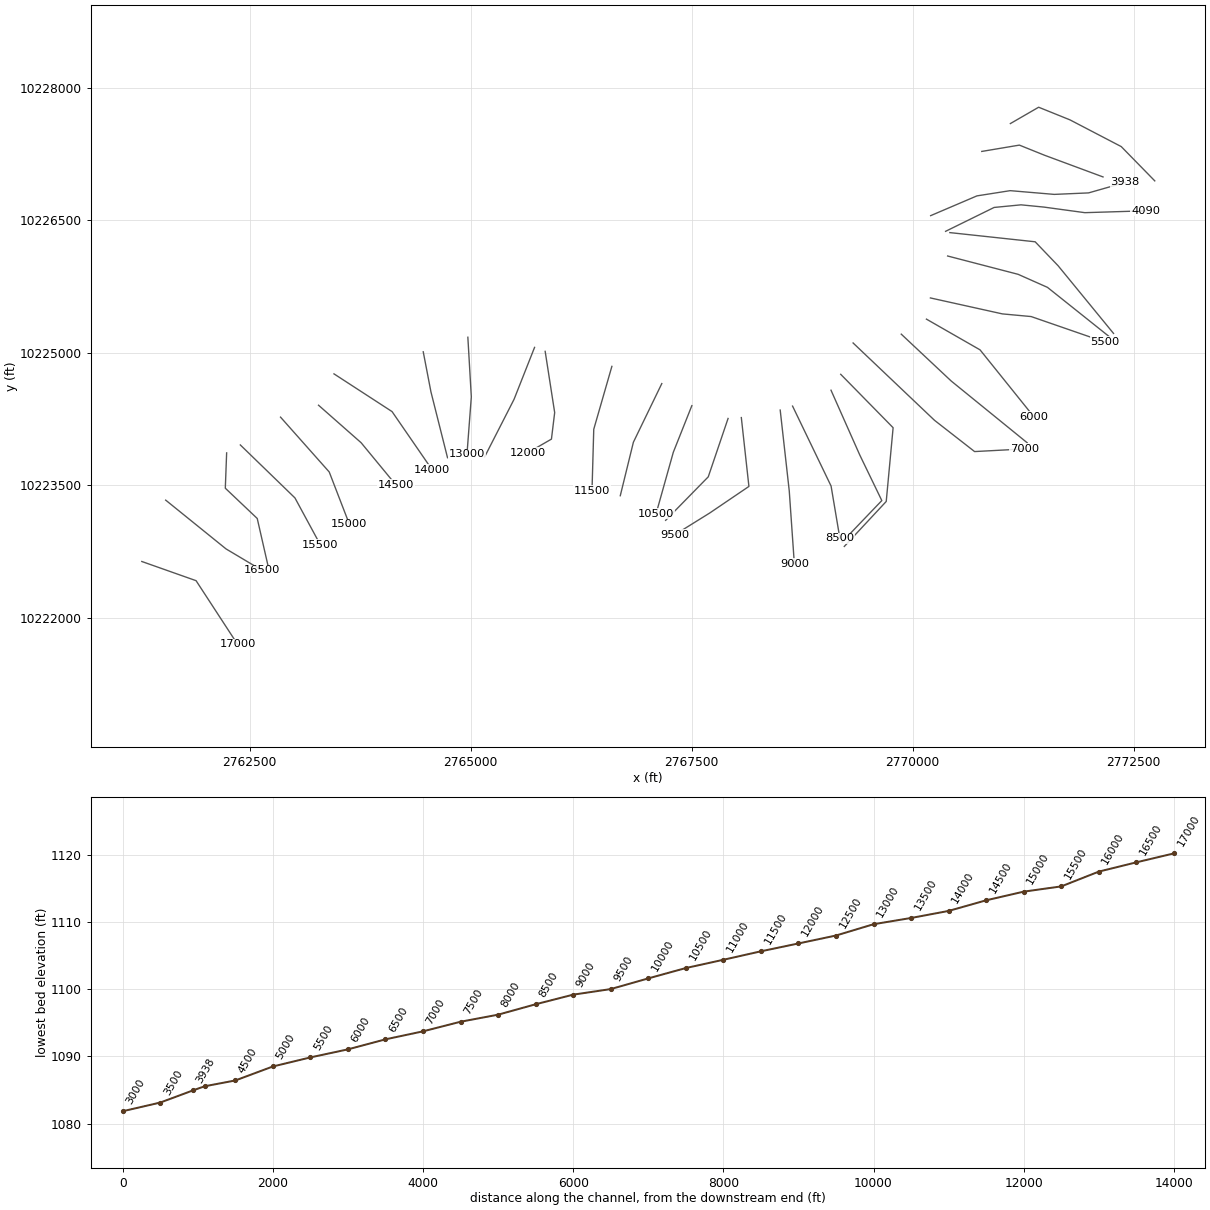
HEC-RAS study HICKORY CREEK.prj: HICKORY CREEK Base Level Engineering

--- HICKORY CREEK.g01 (geometry) --- (continued)

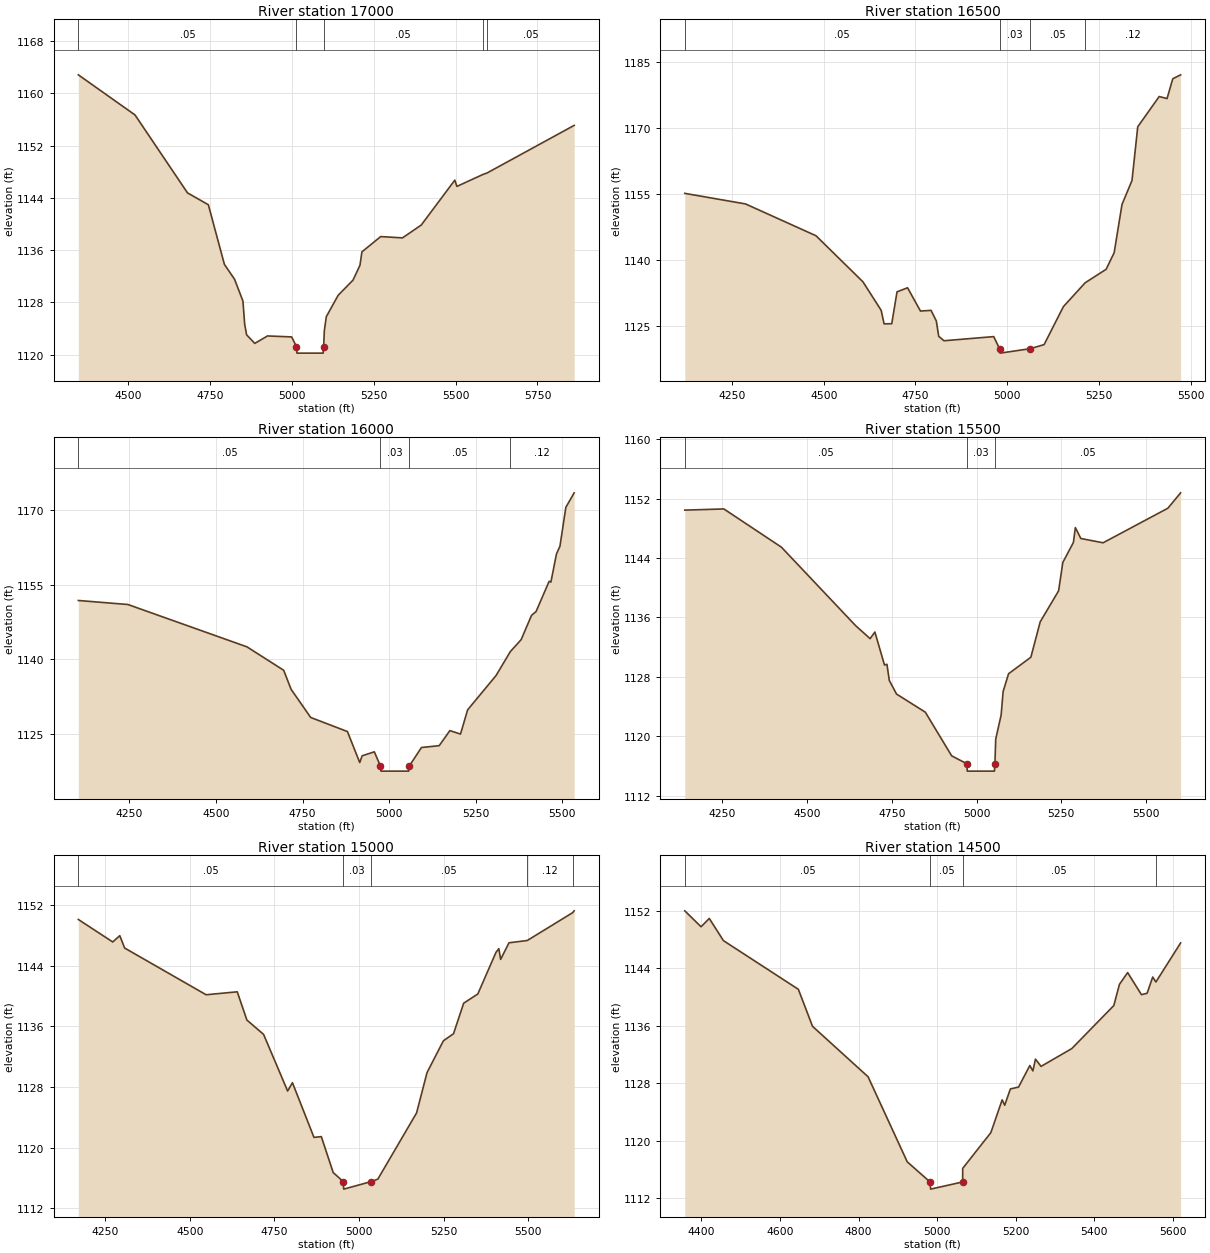
Type RM Length L Ch R = 1 ,17000   ,500,500,500
BEGIN DESCRIPTION:
HICKORY CREEK 34.0
END DESCRIPTION:
XS GIS Cut Line= 3
      2761281.66      10222637.2       2761895.2     10222420.14
      2762365.75     10221698.03
#Sta/Elev= 30
  4349.2 1162.82  4522.1 1156.68  4682.3 1144.75  4745.9 1142.93  4794.9  1133.8
  4825.8 1131.53  4851.4 1128.19  4856.7 1124.65  4862.6 1123.02  4887.6 1121.71
  4926.3 1122.85    5000  1122.7  5014.7 1121.22  5016.2 1120.22  5096.1 1120.22
  5097.6 1121.22  5099.8 1123.69  5105.7 1125.79    5142 1129.08  5187.3  1131.4
  5208.4 1133.67  5214.4 1135.72  5271.7 1138.06  5338.2 1137.86  5395.5 1139.83
  5497.8  1146.7  5504.2 1145.74  5583.3 1147.56  5596.8 1147.81  5861.9 1155.08
#Mann= 5 ,-1 , 0
  4349.2     .05       0  5014.7     .03       0  5097.6     .05       0
  5583.3     .12       0  5596.8     .05       0
Bank Sta=5014.7,5097.6
XS Rating Curve= 0 ,0
Exp/Cntr=0.3,0.1

Type RM Length L Ch R = 1 ,16500   ,500,500,500
BEGIN DESCRIPTION:
HICKORY CREEK 33.0
END DESCRIPTION:
XS GIS Cut Line= 3
      2761551.46     10223331.66       2762234.4      10222779.4
      2762639.93     10222537.69
#Sta/Elev= 30
  4121.7 1155.16  4287.1 1152.76    4479 1145.54  4606.9 1135.08  4656.5 1128.61
  4664.5 1125.54  4685.3 1125.56  4699.7  1132.8  4728.4 1133.73  4763.6 1128.44
  4792.4  1128.6  4806.8 1126.18  4813.2 1122.72  4827.6  1121.7  4963.1 1122.64
    4979 1119.89  4980.5 1118.89    5062 1119.89  5100.3 1120.82  5152.8 1129.44
  5212.1 1134.86  5269.2 1137.92  5291.1 1141.69  5312.5 1152.66  5339.7 1158.09
  5355.3 1170.27  5413.7 1177.14  5435.1 1176.68  5450.7 1181.17  5472.1 1182.07
#Mann= 4 ,-1 , 0
  4121.7     .05       0    4979     .03       0    5062     .05       0
  5212.1     .12       0
Bank Sta=4979,5062
XS Rating Curve= 0 ,0
Exp/Cntr=0.3,0.1

Type RM Length L Ch R = 1 ,16000   ,500,500,500
BEGIN DESCRIPTION:
HICKORY CREEK 32.0
END DESCRIPTION:
XS GIS Cut Line= 4
      2762240.91     10223866.26      2762225.92     10223466.57
        2762587.     10223123.99      2762705.68     10222603.14
#Sta/Elev= 30
  4102.3 1151.83  4245.5 1151.02  4589.4  1142.5  4695.4 1137.79  4716.8 1133.96
  4773.4  1128.3  4879.4 1125.47    4915 1119.24  4921.9 1120.59  4957.1 1121.39
  4974.9 1118.51  4976.4 1117.51  5056.4 1117.51  5057.9 1118.51  5093.2 1122.26
  5144.5 1122.63  5175.3 1125.66    5206 1124.96  5226.5 1129.83  5308.6 1136.73
  5349.9 1141.55  5381.1 1143.95  5411.2 1148.85  5424.1 1149.59    5462 1155.69
  5467.1 1155.53    5483 1161.16  5493.2 1162.75  5510.2 1170.56  5534.2 1173.48
#Mann= 4 ,-1 , 0
  4102.3     .05       0  4974.9     .03       0  5057.9     .05       0
  5349.9     .12       0
Bank Sta=4974.9,5057.9
XS Rating Curve= 0 ,0
Exp/Cntr=0.3,0.1

Type RM Length L Ch R = 1 ,15500   ,500,500,500
BEGIN DESCRIPTION:
HICKORY CREEK 31.0
END DESCRIPTION:
XS GIS Cut Line= 3
       2762395.8     10223956.18      2763013.37     10223356.82
      2763299.82     10222827.56
#Sta/Elev= 30
  4139.4 1150.46  4254.6 1150.62  4424.4 1145.47  4643.5 1134.89    4686 1133.15
  4700.1 1134.04  4728.4  1129.6  4735.6  1129.7  4742.6 1127.52  4763.9 1125.69
  4848.8 1123.25  4926.5 1117.37  4971.1 1116.31  4972.6 1115.31  5052.6 1115.31
  5054.1 1116.31  5056.4 1119.61  5072.4 1122.87  5078.3 1126.03  5094.4 1128.43
  5160.1 1130.65  5187.6 1135.41  5241.9 1139.59  5254.4 1143.42  5285.6 1146.11
  5291.3 1148.11  5307.5 1146.64  5373.1 1146.06  5564.3 1150.72  5601.8 1152.79
#Mann= 3 ,-1 , 0
  4139.4     .05       0  4971.1     .03       0  5054.1     .05       0
Bank Sta=4971.1,5054.1
XS Rating Curve= 0 ,0
Exp/Cntr=0.3,0.1

Type RM Length L Ch R = 1 ,15000   ,500,500,500
BEGIN DESCRIPTION:
HICKORY CREEK 30.0
END DESCRIPTION:
XS GIS Cut Line= 3
      2762850.41     10224270.98      2763401.01     10223650.43
      2763629.61     10223057.47
#Sta/Elev= 30
  4170.4 1150.13    4272 1147.16  4292.9 1147.99  4307.2 1146.36    4548 1140.19
    4640 1140.58  4668.5 1136.85  4717.8 1134.96  4788.9 1127.48  4803.1 1128.58
  4866.7 1121.36  4888.4 1121.46  4923.5 1116.72  4953.1 1115.53  4954.6 1114.53
  5036.1 1115.53  5055.4 1115.85  5169.9 1124.59  5200.8 1129.92  5249.1 1134.11
  5279.1 1135.05  5309.1 1139.08  5350.8 1140.29  5404.4 1145.78  5412.9 1146.28
  5418.3 1144.86  5442.9 1147.05  5496.8 1147.35  5630.8 1151.02  5635.5 1151.27
#Mann= 5 ,-1 , 0
  4170.4     .05       0  4953.1     .03       0  5036.1     .05       0
  5496.8     .12       0  5630.8     .05       0
Bank Sta=4953.1,5036.1
XS Rating Curve= 0 ,0
Exp/Cntr=0.3,0.1

Type RM Length L Ch R = 1 ,14500   ,500,500,500
BEGIN DESCRIPTION:
HICKORY CREEK 29.0
END DESCRIPTION:
XS GIS Cut Line= 3
      2763280.09     10224405.86      2763761.97     10223981.19
      2764155.66     10223503.14
#Sta/Elev= 30
  4357.7 1151.99  4399.1 1149.77    4420 1150.93    4456 1147.84  4646.7 1141.06
  4682.7 1135.91  4824.1 1128.88  4923.7 1117.04  4981.7 1114.24  4983.2 1113.24
  5064.7 1114.24  5064.8 1116.13  5136.5 1121.11  5165.2 1125.67  5171.7 1124.92
  5186.1 1127.19  5206.9 1127.45  5235.6 1130.45  5243.4  1129.7  5249.9 1131.34
  5264.2 1130.33  5342.4 1132.81  5449.3  1138.8  5463.6 1141.75  5484.5 1143.39
  5519.6 1140.32    5534 1140.51  5548.3 1142.77  5556.4 1142.08  5619.3 1147.52
#Mann= 4 ,-1 , 0
  4357.7     .05       0  4981.7     .05       0  5064.7     .05       0
  5556.4     .12       0
Bank Sta=4981.7,5064.7
XS Rating Curve= 0 ,0
Exp/Cntr=0.3,0.1

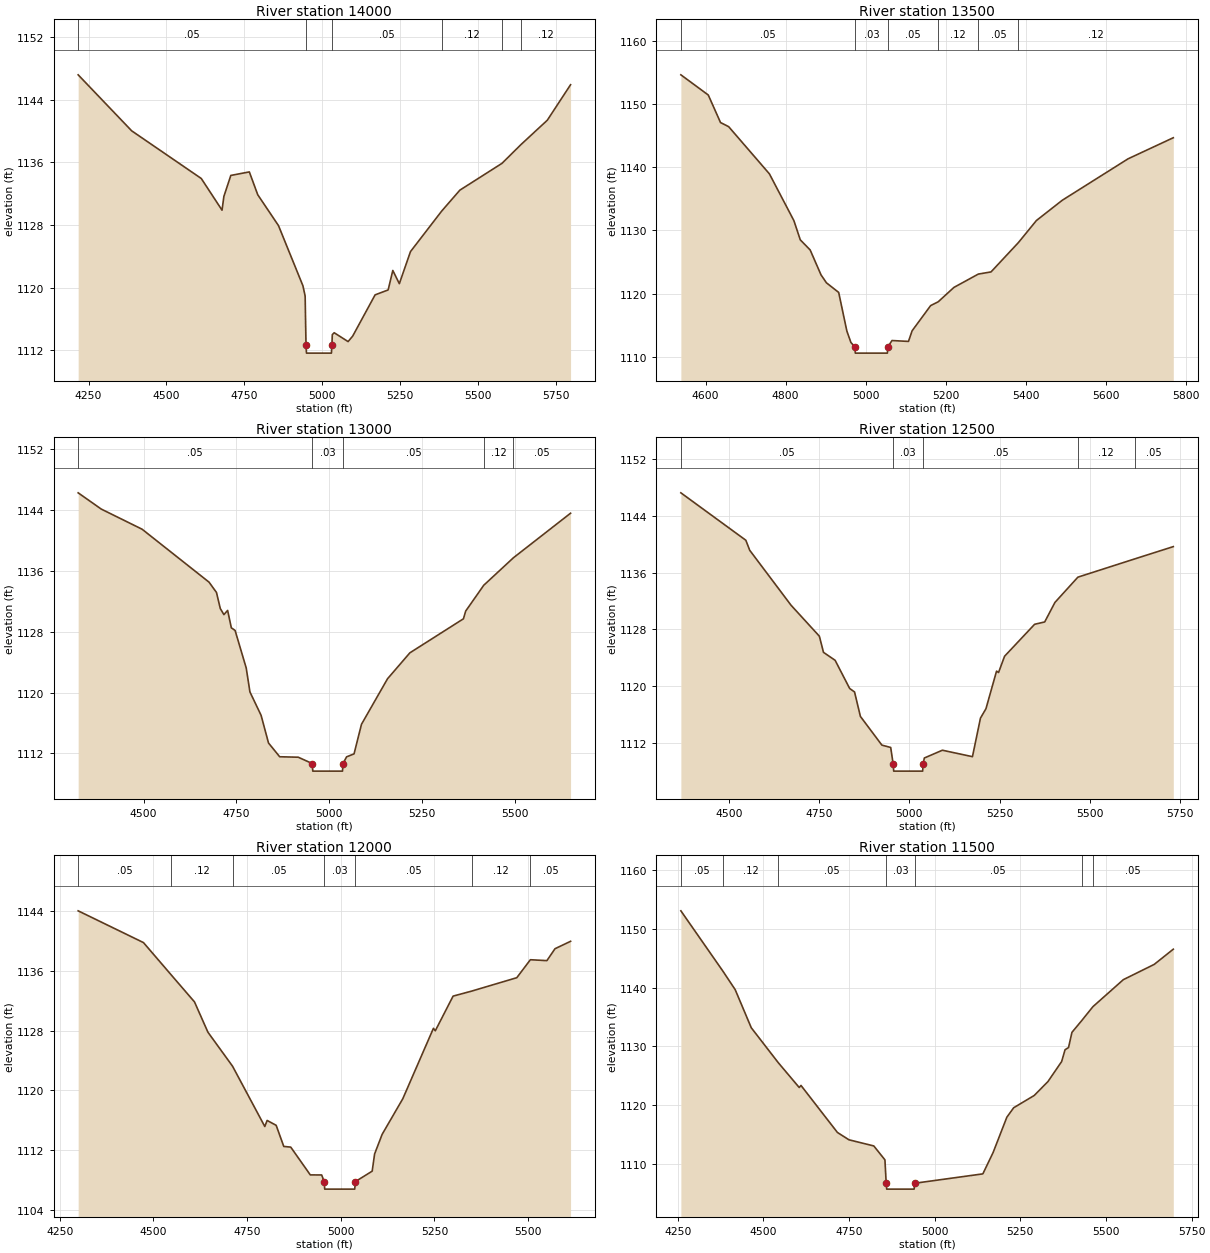
Type RM Length L Ch R = 1 ,14000   ,500,500,500
BEGIN DESCRIPTION:
HICKORY CREEK 28.0
END DESCRIPTION:
XS GIS Cut Line= 3
      2763454.95     10224760.59      2764111.69     10224333.68
      2764563.53     10223677.26
#Sta/Elev= 30
  4216.7 1147.15  4388.4 1140.01  4611.8 1133.93  4678.4 1129.89  4684.3 1131.64
  4706.6 1134.32    4766 1134.77    4793 1131.86  4859.6 1127.92    4938 1120.25
  4945.1 1118.94  4947.9 1112.66  4949.4 1111.66  5029.4 1111.66  5030.9 1112.66
  5032.3 1114.02  5038.3 1114.26    5083 1113.13  5097.8 1113.84  5169.6 1119.09
  5211.5 1119.72  5226.4  1122.2  5247.4 1120.52  5283.2 1124.61  5383.2 1129.77
  5441.5 1132.44  5576.7 1135.86  5638.1 1138.27  5722.2 1141.36  5796.9 1145.89
#Mann= 6 ,-1 , 0
  4216.7     .05       0  4947.9     .03       0  5030.9     .05       0
  5383.2     .12       0  5576.7     .05       0  5638.1     .12       0
Bank Sta=4947.9,5030.9
XS Rating Curve= 0 ,0
Exp/Cntr=0.3,0.1

Type RM Length L Ch R = 1 ,13500   ,500,500,500
BEGIN DESCRIPTION:
HICKORY CREEK 27.0
END DESCRIPTION:
XS GIS Cut Line= 3
      2764464.19      10225010.4      2764551.38     10224557.01
      2764738.97     10223811.34
#Sta/Elev= 30
  4538.3 1154.58  4606.8 1151.39  4637.4 1147.04  4657.7 1146.39  4759.6 1138.93
  4820.7 1131.55  4836.7 1128.51  4861.4 1126.91  4888.6 1122.97  4902.1 1121.72
  4932.7  1120.2  4953.1  1114.1  4963.2  1112.3  4972.8 1111.61  4974.3 1110.61
  5054.3 1110.61  5055.8 1111.61  5065.9  1112.6  5107.1 1112.46  5116.2 1114.14
  5162.5 1118.12  5181.4 1118.72  5220.6 1120.99  5281.7  1123.1  5313.4 1123.44
  5381.9 1128.08  5426.8 1131.56  5491.4 1134.76  5655.9 1141.31  5768.9 1144.64
#Mann= 6 ,-1 , 0
  4538.3     .05       0  4972.8     .03       0  5055.8     .05       0
  5181.4     .12       0  5281.7     .05       0  5381.9     .12       0
Bank Sta=4972.8,5055.8
XS Rating Curve= 0 ,0
Exp/Cntr=0.3,0.1

Type RM Length L Ch R = 1 ,13000   ,500,500,500
BEGIN DESCRIPTION:
HICKORY CREEK 26.0
END DESCRIPTION:
XS GIS Cut Line= 3
       2764968.8     10225175.27      2765007.94       10224500.
      2764958.81     10223851.26
#Sta/Elev= 30
  4323.6 1146.29  4385.9 1144.15    4496  1141.5  4676.3 1134.54  4696.4 1133.18
  4706.6 1131.07  4716.4 1130.27  4726.4 1130.82  4736.4 1128.53  4746.5 1128.19
  4776.5 1123.25  4786.5  1120.1  4816.6 1117.02  4836.6 1113.38  4866.7 1111.57
  4916.7 1111.51  4954.4 1110.68  4955.9 1109.68  5035.9 1109.68  5037.4 1110.68
    5047 1111.56  5067.1 1111.95  5087.1 1115.84  5157.3 1121.83  5217.5 1125.24
  5361.9 1129.72  5367.9 1130.73  5416.6 1134.13  5496.4 1137.74  5650.6 1143.61
#Mann= 5 ,-1 , 0
  4323.6     .05       0  4954.4     .03       0  5037.4     .05       0
  5416.6     .12       0  5496.4     .05       0
Bank Sta=4954.4,5037.4
XS Rating Curve= 0 ,0
Exp/Cntr=0.3,0.1

Type RM Length L Ch R = 1 ,12500   ,500,500,500
BEGIN DESCRIPTION:
HICKORY CREEK 25.0
END DESCRIPTION:
XS GIS Cut Line= 3
      2765723.22     10225060.33        2765491.       10224472.
      2765158.64     10223821.26
#Sta/Elev= 30
  4367.5 1147.27  4547.3 1140.58    4558 1139.17  4672.5 1131.41  4750.9 1127.04
  4762.3 1124.76  4794.5 1123.64  4834.8 1119.66  4848.3 1119.17  4864.5 1115.72
    4924 1111.67  4948.4 1111.34  4955.2    1109  4956.7    1108  5036.8    1108
  5038.3    1109  5041.4 1109.85  5091.4 1110.95  5174.7 1110.04  5196.9 1115.48
  5212.1 1116.81  5241.4 1122.11    5247 1121.92  5263.6 1124.21  5346.8 1128.72
  5374.7 1129.05    5403  1131.8  5466.6 1135.37  5624.2 1137.95  5730.7 1139.68
#Mann= 5 ,-1 , 0
  4367.5     .05       0  4955.2     .03       0  5038.3     .05       0
  5466.6     .12       0  5624.2     .05       0
Bank Sta=4955.2,5038.3
XS Rating Curve= 0 ,0
Exp/Cntr=0.3,0.1

Type RM Length L Ch R = 1 ,12000   ,500,500,500
BEGIN DESCRIPTION:
HICKORY CREEK 24.0
END DESCRIPTION:
XS GIS Cut Line= 4
      2765843.13     10225015.38      2765950.64     10224322.78
      2765914.09     10224022.23       2765644.9     10223867.19
#Sta/Elev= 30
  4299.1 1143.98  4473.4 1139.74    4546 1135.51  4609.6 1131.82  4645.5 1127.77
  4711.1 1123.24  4797.3 1115.18  4803.5 1115.99  4827.6 1115.34  4847.9 1112.52
  4866.5 1112.43  4918.7 1108.72  4949.1 1108.71  4955.7 1107.82  4957.2 1106.82
  5037.3 1106.82  5038.8 1107.82  5083.9 1109.22  5090.3 1111.51  5110.5 1114.14
  5165.6 1118.89  5247.3 1128.29  5252.3 1127.96  5299.8 1132.59  5349.3 1133.26
  5469.8 1135.05  5506.1 1137.45  5550.2 1137.33  5571.8 1138.92  5613.4 1139.91
#Mann= 7 ,-1 , 0
  4299.1     .05       0    4546     .12       0  4711.1     .05       0
  4955.7     .03       0  5038.8     .05       0  5349.3     .12       0
  5506.1     .05       0
Bank Sta=4955.7,5038.8
XS Rating Curve= 0 ,0
Exp/Cntr=0.3,0.1

Type RM Length L Ch R = 1 ,11500   ,500,500,500
BEGIN DESCRIPTION:
HICKORY CREEK 23.0
END DESCRIPTION:
XS GIS Cut Line= 3
      2766597.54     10224845.49      2766392.58     10224133.51
      2766372.74     10223437.39
#Sta/Elev= 30
  4259.1 1153.08    4382 1142.78  4417.7 1139.64  4464.6 1133.15  4543.1 1127.22
  4604.5 1122.97  4609.7 1123.32    4716 1115.31  4749.6 1114.06  4822.2 1113.01
  4854.7 1110.64  4858.4 1106.65  4859.9 1105.65    4940 1105.65  4941.5 1106.65
  5140.5 1108.25  5170.5 1111.89  5210.5  1117.9  5230.5 1119.52  5290.5 1121.61
  5330.5 1123.98  5370.5 1127.39  5380.5 1129.41  5390.6 1129.78  5400.6 1132.37
  5429.1 1134.37  5461.7 1136.74  5550.6 1141.35  5640.7 1143.95  5696.4 1146.54
#Mann= 7 ,-1 , 0
  4259.1     .05       0    4382     .12       0  4543.1     .05       0
  4858.4     .03       0  4941.5     .05       0  5429.1     .12       0
  5461.7     .05       0
Bank Sta=4858.4,4941.5
XS Rating Curve= 0 ,0
Exp/Cntr=0.3,0.1

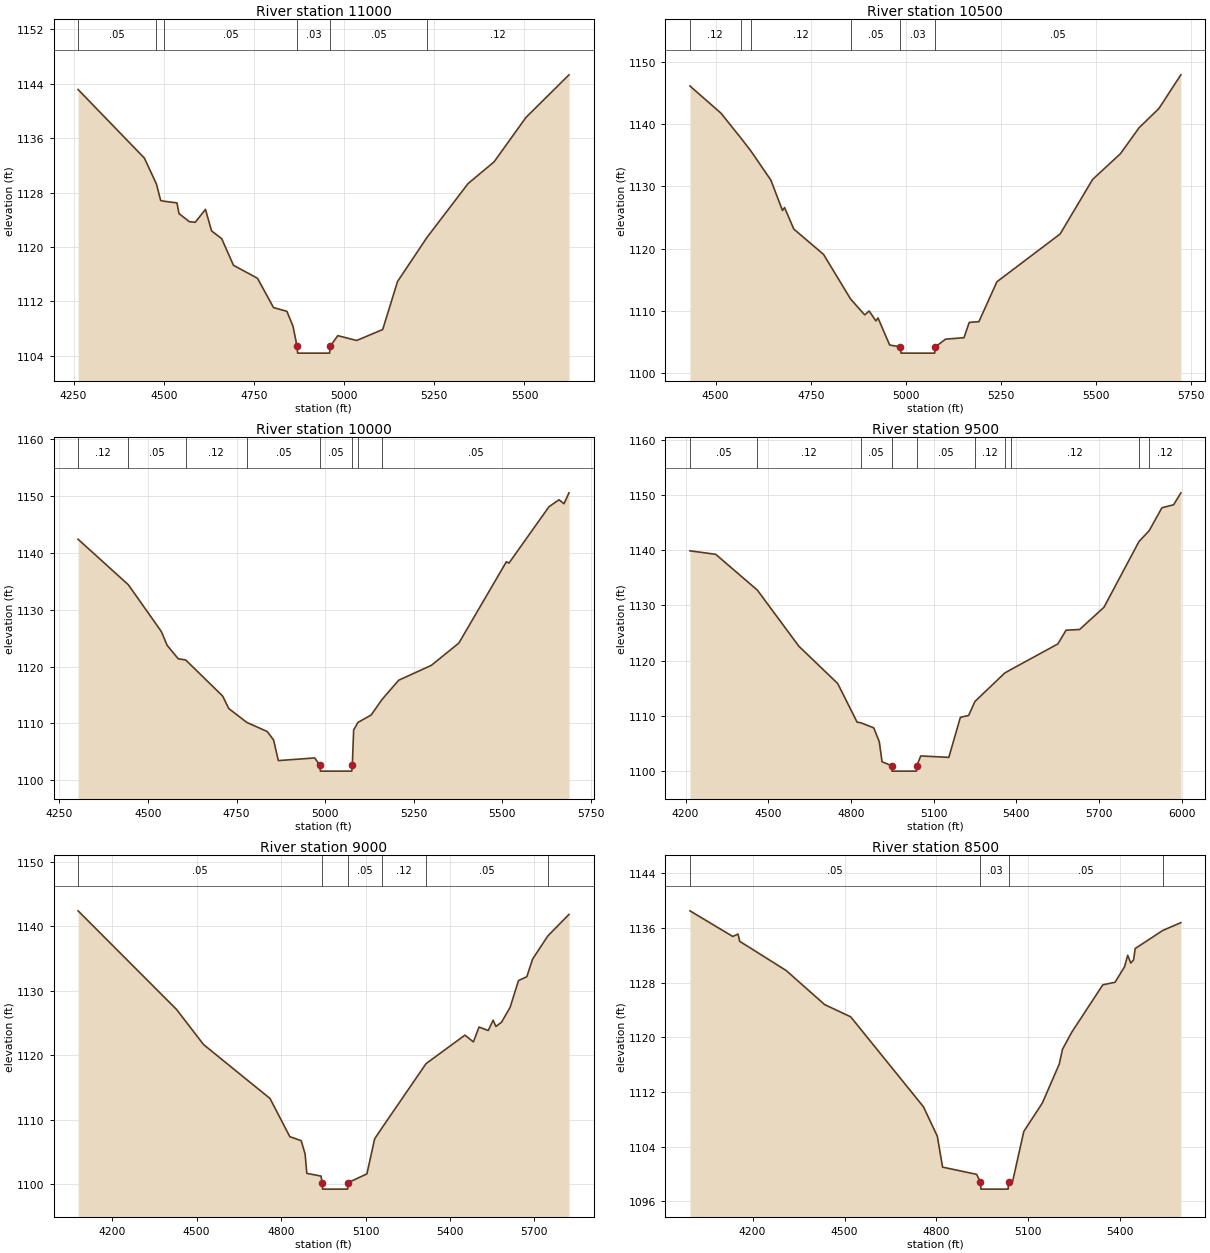
Type RM Length L Ch R = 1 ,11000   ,500,500,500
BEGIN DESCRIPTION:
HICKORY CREEK 22.0
END DESCRIPTION:
XS GIS Cut Line= 3
      2767162.13     10224650.69      2766840.83     10223987.07
      2766692.46     10223381.59
#Sta/Elev= 30
  4262.7 1143.17  4446.5 1133.08  4479.9 1129.26  4491.6 1126.85  4499.9 1126.74
  4536.8 1126.49  4542.4 1124.92  4571.1 1123.73  4587.5 1123.64  4615.7 1125.54
  4632.7 1122.37  4660.8 1121.23  4693.3 1117.32    4760  1115.4  4804.4 1111.09
  4841.5 1110.54  4858.5 1108.33  4869.7 1105.39  4871.2 1104.39  4959.8 1104.39
  4961.3 1105.39  4982.6 1106.96    5035 1106.25    5107 1107.86  5148.2 1114.93
    5230 1121.43  5343.8 1129.34  5415.8 1132.53  5504.1 1139.06  5623.4 1145.33
#Mann= 6 ,-1 , 0
  4262.7     .05       0  4479.9     .12       0  4499.9     .05       0
  4869.7     .03       0  4961.3     .05       0    5230     .12       0
Bank Sta=4869.7,4961.3
XS Rating Curve= 0 ,0
Exp/Cntr=0.3,0.1

Type RM Length L Ch R = 1 ,10500   ,500,500,500
BEGIN DESCRIPTION:
HICKORY CREEK 21.0
END DESCRIPTION:
XS GIS Cut Line= 3
      2767501.83     10224400.81      2767292.36      10223873.6
      2767097.36      10223177.5
#Sta/Elev= 30
  4432.7 1146.17    4514 1141.81  4565.7 1137.86  4592.5 1135.74  4645.4 1131.01
  4675.9 1126.12  4681.3  1126.6  4705.6 1123.14  4783.9 1119.05  4854.8 1111.88
  4891.9 1109.32  4903.7 1109.94  4921.6 1108.34  4926.9 1108.83  4957.5 1104.47
  4985.9 1104.16  4987.4 1103.16    5076 1103.16  5077.5 1104.16  5104.4 1105.41
  5152.8 1105.64  5166.7 1108.11  5192.1 1108.23  5239.4 1114.65  5405.5 1122.34
    5491 1131.13  5564.4 1135.29  5613.2 1139.46  5665.1 1142.54  5722.9 1147.97
#Mann= 6 ,-1 , 0
  4432.7     .12       0  4565.7     .05       0  4592.5     .12       0
  4854.8     .05       0  4985.9     .03       0  5077.5     .05       0
Bank Sta=4985.9,5077.5
XS Rating Curve= 0 ,0
Exp/Cntr=0.3,0.1

Type RM Length L Ch R = 1 ,10000   ,500,500,500
BEGIN DESCRIPTION:
HICKORY CREEK 20.0
END DESCRIPTION:
XS GIS Cut Line= 3
      2767911.54     10224255.98      2767687.61     10223595.51
      2767205.67      10223103.1
#Sta/Elev= 30
  4302.6 1142.37  4444.6 1134.37  4537.9 1126.14  4554.1 1123.73  4585.5 1121.36
  4606.5 1121.16  4711.1  1114.8    4728 1112.63  4779.1 1110.18  4836.8 1108.58
  4854.7  1107.1  4868.2 1103.47  4970.9 1103.94  4985.5 1102.62    4987 1101.62
  5075.6 1101.62  5077.1 1102.62  5080.8 1108.84  5092.9 1110.18  5130.3 1111.48
  5160.8  1114.2  5208.1  1117.6    5300  1120.2  5377.9 1124.12  5512.2 1138.42
  5519.3 1138.17  5632.5 1148.09  5660.8 1149.31  5674.9 1148.62    5689 1150.53
#Mann= 8 ,-1 , 0
  4302.6     .12       0  4444.6     .05       0  4606.5     .12       0
  4779.1     .05       0  4985.5     .05       0  5077.1     .05       0
  5092.9     .12       0  5160.8     .05       0
Bank Sta=4985.5,5077.1
XS Rating Curve= 0 ,0
Exp/Cntr=0.3,0.1

Type RM Length L Ch R = 1 ,9500    ,500,500,500
BEGIN DESCRIPTION:
HICKORY CREEK 19.0
END DESCRIPTION:
XS GIS Cut Line= 4
      2768061.42     10224265.96      2768147.24     10223486.77
      2767704.05     10223185.94        2767312.     10222941.98
#Sta/Elev= 30
  4216.1 1139.88  4309.5 1139.25  4460.7 1132.77  4611.3 1122.62  4752.2 1115.88
  4822.6 1108.89  4835.9 1108.78    4883 1107.86  4903.1 1105.36  4913.1 1101.72
  4947.7 1101.03  4949.2 1100.03    5038 1100.03  5039.5 1101.03  5053.6 1102.78
  5155.4 1102.52  5197.4 1109.76  5227.3  1110.1    5250 1112.62  5358.1 1117.77
  5379.4 1118.37  5550.9 1123.03  5580.8 1125.52    5630 1125.65  5718.5 1129.68
  5845.3 1141.55  5882.5 1143.53  5928.6 1147.67  5971.1 1148.21  5997.4 1150.37
#Mann= 10 ,-1 , 0
  4216.1     .05       0  4460.7     .12       0  4835.9     .05       0
  4947.7     .03       0  5039.5     .05       0    5250     .12       0
  5358.1     .05       0  5379.4     .12       0  5845.3     .05       0
  5882.5     .12       0
Bank Sta=4947.7,5039.5
XS Rating Curve= 0 ,0
Exp/Cntr=0.3,0.1

Type RM Length L Ch R = 1 ,9000    ,500,500,500
BEGIN DESCRIPTION:
HICKORY CREEK 18.0
END DESCRIPTION:
XS GIS Cut Line= 3
      2768501.08     10224350.87      2768603.56     10223435.19
      2768660.82     10222614.19
#Sta/Elev= 30
  4078.6 1142.43  4428.5 1127.11  4524.4 1121.66  4760.6 1113.28    4831 1107.35
  4871.3 1106.73  4885.3 1104.66  4891.4 1101.65  4941.7 1101.23  4946.1  1100.2
  4947.6  1099.2  5036.4  1099.2  5037.9  1100.2  5104.9 1101.57  5132.4 1107.01
  5158.4 1108.71  5315.2  1118.7  5453.2 1123.12  5483.3 1122.07  5503.3 1124.38
    5536 1123.84  5553.4 1125.44  5563.4 1124.47  5583.5 1125.14  5613.6 1127.42
  5643.6  1131.6    5673 1132.19  5693.8 1134.94  5747.6 1138.52    5823 1141.88
#Mann= 6 ,-1 , 0
  4078.6     .05       0  4946.1     .05       0  5037.9     .05       0
  5158.4     .12       0  5315.2     .05       0  5747.6     .12       0
Bank Sta=4946.1,5037.9
XS Rating Curve= 0 ,0
Exp/Cntr=0.3,0.1

Type RM Length L Ch R = 1 ,8500    ,500,500,500
BEGIN DESCRIPTION:
HICKORY CREEK 17.0
END DESCRIPTION:
XS GIS Cut Line= 3
      2768640.97     10224395.84       2769076.5       10223491.
      2769175.56     10222901.97
#Sta/Elev= 30
  3995.8 1138.49  4135.5 1134.74  4152.6 1135.09  4158.1 1134.03  4309.6 1129.76
  4435.2 1124.77  4520.2 1122.98  4757.5 1109.82  4802.8 1105.51  4819.9 1100.99
  4931.1 1099.93  4943.5 1098.77    4945 1097.77  5033.8 1097.77  5035.3 1098.77
  5048.6 1098.93  5084.8  1106.2  5145.4 1110.37  5200.7 1116.08    5211 1118.22
  5241.2 1120.72  5342.6 1127.66  5382.6 1128.04  5413.6 1130.31  5423.8 1131.99
  5433.9 1130.85  5443.1 1131.32  5448.2 1132.97  5538.7 1135.63  5597.3 1136.76
#Mann= 4 ,-1 , 0
  3995.8     .05       0  4943.5     .03       0  5035.3     .05       0
  5538.7     .12       0
Bank Sta=4943.5,5035.3
XS Rating Curve= 0 ,0
Exp/Cntr=0.3,0.1

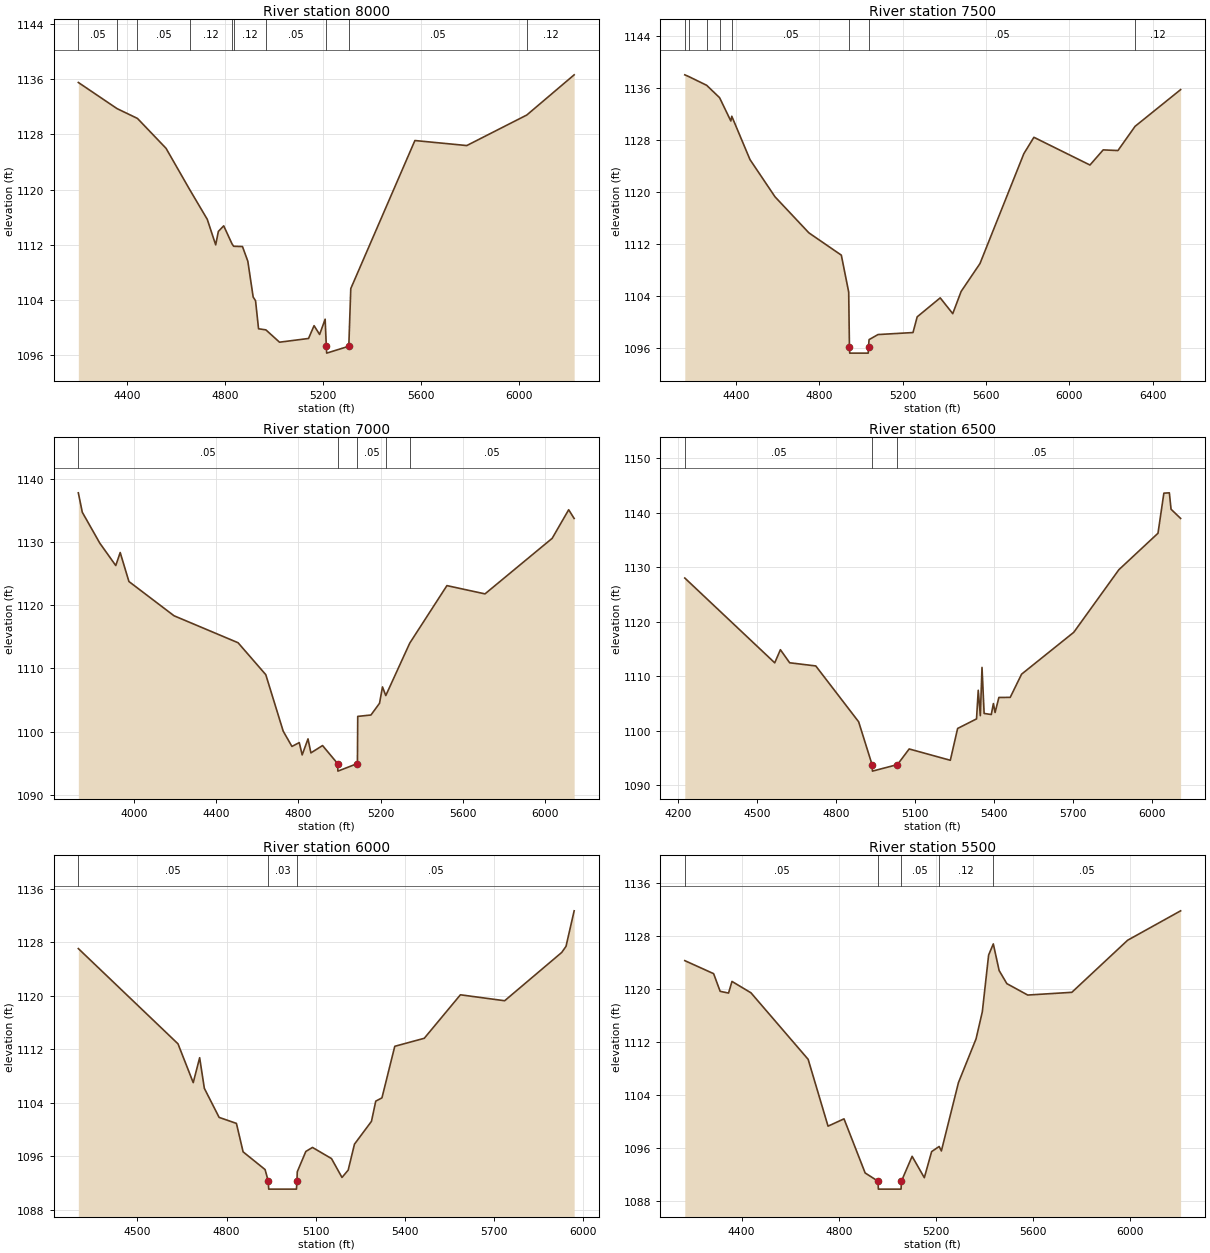
Type RM Length L Ch R = 1 ,8000    ,500,500,500
BEGIN DESCRIPTION:
HICKORY CREEK 16.0
END DESCRIPTION:
XS GIS Cut Line= 4
      2769075.63     10224575.71      2769400.15     10223844.05
      2769650.19     10223326.68       2769201.1     10222857.63
#Sta/Elev= 30
  4199.6 1135.56  4357.6 1131.76  4441.1 1130.33  4557.7 1125.99  4653.6 1120.03
    4726 1115.67  4760.4 1111.96  4771.3 1113.91  4793.2 1114.72    4827 1112.11
  4833.7 1111.75  4869.8 1111.71  4891.6 1109.58  4913.5 1104.37  4923.2 1103.83
  4935.4 1099.76  4965.4  1099.6    5021 1097.81  5139.5 1098.35  5162.1 1100.21
  5184.7 1098.93  5207.3 1101.15  5212.1 1097.22  5213.6 1096.22  5303.9 1097.22
    5312  1105.6  5573.8 1127.12  5785.6 1126.39  6030.7 1130.83    6224 1136.67
#Mann= 10 ,-1 , 0
  4199.6     .05       0  4357.6     .12       0  4441.1     .05       0
  4653.6     .12       0    4827     .05       0  4833.7     .12       0
  4965.4     .05       0  5212.1     .03       0  5303.9     .05       0
  6030.7     .12       0
Bank Sta=5212.1,5303.9
XS Rating Curve= 0 ,0
Exp/Cntr=0.3,0.1

Type RM Length L Ch R = 1 ,7500    ,500,500,500
BEGIN DESCRIPTION:
HICKORY CREEK 15.0
END DESCRIPTION:
XS GIS Cut Line= 4
      2769185.56     10224755.56      2769778.02     10224151.23
      2769700.15     10223316.68      2769225.98     10222807.57
#Sta/Elev= 30
  4153.7 1138.03    4173 1137.76  4258.6 1136.42  4320.7 1134.51  4374.7 1130.92
  4379.3 1131.65  4466.6 1124.98  4586.9 1119.24  4749.5 1113.69  4905.1 1110.26
  4940.5 1104.58    4944 1096.17  4945.5 1095.17  5034.3 1095.17  5035.8 1096.17
  5038.3 1097.25  5081.2 1098.03  5249.2 1098.34  5269.3 1100.76  5379.8 1103.68
    5440 1101.25  5480.2 1104.67  5570.6 1108.96  5781.5  1125.9  5829.6 1128.41
  6098.7 1124.14  6162.2 1126.47    6233 1126.37  6315.3  1130.1  6533.9 1135.75
#Mann= 8 ,-1 , 0
  4153.7     .05       0    4173     .12       0  4258.6     .05       0
  4320.7     .12       0  4379.3     .05       0    4944     .03       0
  5035.8     .05       0  6315.3     .12       0
Bank Sta=4944,5035.8
XS Rating Curve= 0 ,0
Exp/Cntr=0.3,0.1

Type RM Length L Ch R = 1 ,7000    ,500,500,500
BEGIN DESCRIPTION:
HICKORY CREEK 14.0
END DESCRIPTION:
XS GIS Cut Line= 4
      2769325.46     10225110.28      2770245.51     10224235.56
      2770699.38     10223881.25       2771262.3     10223911.14
#Sta/Elev= 30
  3730.5 1137.83  3749.8 1134.75  3834.8 1129.86  3912.4 1126.31  3933.9 1128.37
  3976.3 1123.78  4195.6 1118.35  4506.6 1114.08  4641.3 1109.02  4725.9 1100.07
  4768.3 1097.65  4803.9 1098.26  4818.1 1096.31  4846.4 1098.85  4860.5 1096.63
  4917.1 1097.79  4990.1 1094.94  4991.6 1093.74  5086.5 1094.94    5088 1102.41
  5152.2 1102.63  5193.9 1104.49  5208.3 1107.08  5224.3 1105.71  5340.6 1114.01
  5521.3 1123.13  5706.3 1121.82  6032.7 1130.62  6112.9 1135.15  6139.5 1133.77
#Mann= 5 ,-1 , 0
  3730.5     .05       0  4990.1     .03       0  5086.5     .05       0
  5224.3     .12       0  5340.6     .05       0
Bank Sta=4990.1,5086.5
XS Rating Curve= 0 ,0
Exp/Cntr=0.3,0.1

Type RM Length L Ch R = 1 ,6500    ,500,500,500
BEGIN DESCRIPTION:
HICKORY CREEK 13.0
END DESCRIPTION:
XS GIS Cut Line= 3
      2769870.05     10225210.19      2770434.09     10224680.44
      2771293.93     10223981.16
#Sta/Elev= 30
  4226.2    1128  4567.6 1112.43  4589.1 1114.84  4624.3 1112.44  4723.4 1111.86
  4886.1 1101.61    4937 1093.75  4938.5 1092.55  5033.4 1093.75  5077.9 1096.62
  5234.1 1094.54  5261.8 1100.38  5333.6 1102.14  5340.1 1107.39    5348 1102.73
  5354.4 1111.59  5362.4 1103.14  5389.6 1102.94  5397.6 1104.95    5404 1103.31
  5418.4 1106.07  5461.5 1106.09  5504.6 1110.35  5702.8 1118.04  5873.8 1129.52
  6022.4 1136.22  6044.7 1143.58  6065.5 1143.64    6072 1140.63  6108.3 1138.94
#Mann= 3 ,-1 , 0
  4226.2     .05       0    4937     .03       0  5033.4     .05       0
Bank Sta=4937,5033.4
XS Rating Curve= 0 ,0
Exp/Cntr=0.3,0.1

Type RM Length L Ch R = 1 ,6000    ,500,500,500
BEGIN DESCRIPTION:
HICKORY CREEK 12.0
END DESCRIPTION:
XS GIS Cut Line= 3
      2770154.84     10225380.07      2770761.13      10225032.4
      2771368.02     10224276.99
#Sta/Elev= 30
  4301.1 1127.07  4636.4 1112.81  4687.6    1107  4709.2 1110.73    4725 1106.15
  4774.7  1101.8  4832.9  1100.9  4855.4 1096.64  4929.3 1093.99    4940 1092.26
  4941.5 1091.06  5034.9 1091.06  5036.4 1092.26  5037.6 1093.66  5066.4  1096.7
  5088.8  1097.3  5152.8 1095.63    5188 1092.81  5208.8  1093.9    5230 1097.79
  5287.2 1101.21  5301.6 1104.23  5322.4 1104.72  5365.6 1112.44  5464.8 1113.64
  5586.4 1120.15  5735.2 1119.26  5927.2 1126.49  5941.6  1127.4    5969 1132.72
#Mann= 3 ,-1 , 0
  4301.1     .05       0    4940     .03       0  5036.4     .05       0
Bank Sta=4940,5036.4
XS Rating Curve= 0 ,0
Exp/Cntr=0.3,0.1

Type RM Length L Ch R = 1 ,5500    ,500,500,500
BEGIN DESCRIPTION:
HICKORY CREEK 11.0
END DESCRIPTION:
XS GIS Cut Line= 4
      2770199.75     10225619.91      2771014.06      10225439.3
      2771338.81     10225409.29      2772171.93     10225120.75
#Sta/Elev= 30
  4165.9 1124.26  4284.6  1122.3  4311.5 1119.64  4346.1 1119.38  4360.2 1121.13
  4438.3 1119.42  4673.9  1109.4  4755.8 1099.34  4821.6 1100.44  4908.7 1092.29
  4961.6 1091.06  4963.1 1089.86  5056.5 1089.86    5058 1091.06  5102.1  1094.8
  5152.3 1091.58  5182.4 1095.51  5213.4 1096.28  5222.6 1095.61  5292.9  1105.9
  5365.4 1112.49  5391.2 1116.57  5417.1  1125.1  5436.4 1126.78  5460.4 1122.77
  5492.1  1120.8  5578.1 1119.08  5759.8 1119.49  5989.5 1127.33  6207.8 1131.76
#Mann= 5 ,-1 , 0
  4165.9     .05       0  4961.6     .03       0    5058     .05       0
  5213.4     .12       0  5436.4     .05       0
Bank Sta=4961.6,5058
XS Rating Curve= 0 ,0
Exp/Cntr=0.3,0.1

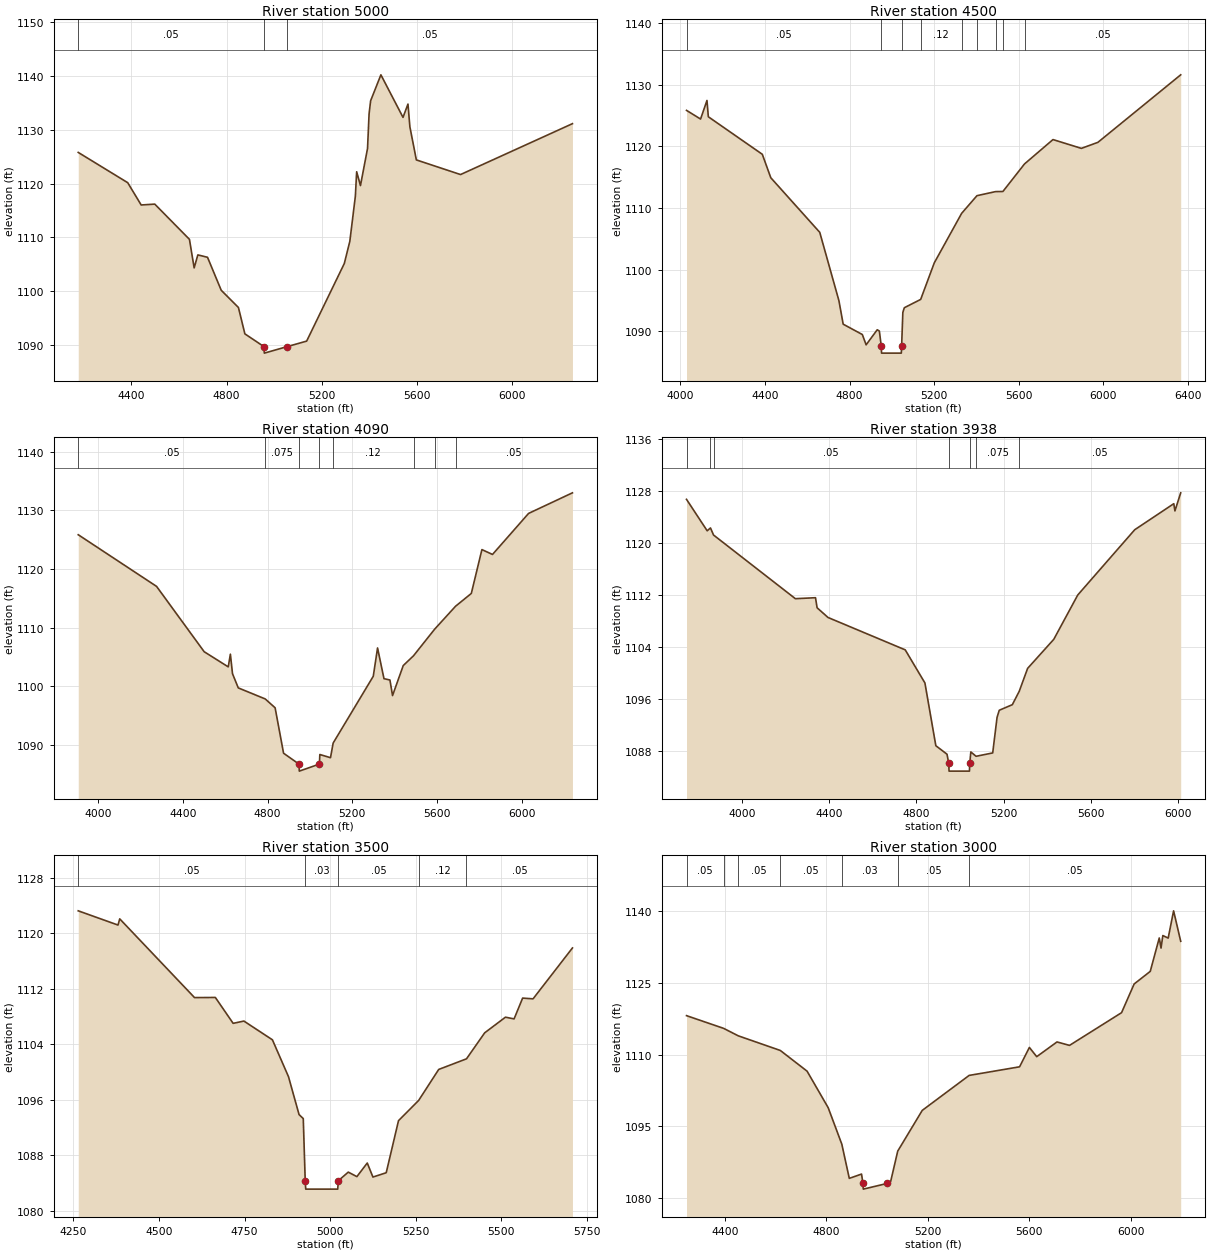
Type RM Length L Ch R = 1 ,5000    ,500,500,500
BEGIN DESCRIPTION:
HICKORY CREEK 10.0
END DESCRIPTION:
XS GIS Cut Line= 4
      2770394.59     10226094.55      2771191.29     10225887.37
      2771523.64     10225739.59      2772218.21     10225185.24
#Sta/Elev= 30
  4176.8 1125.78  4384.6 1120.16  4441.1 1116.02  4498.2 1116.18  4643.8 1109.64
  4663.6 1104.34  4679.1 1106.75  4719.7 1106.31  4777.2 1100.19  4849.6 1096.98
  4876.6 1092.09  4956.9 1089.71  4958.4 1088.51  5053.3 1089.71  5136.1 1090.74
  5294.2 1105.15  5317.4 1109.27  5340.7 1117.67  5346.1 1122.19  5362.1 1119.63
  5391.8 1126.52  5398.2 1132.91  5404.7 1135.36  5447.9 1140.19  5540.8 1132.29
  5561.6 1134.76  5569.6 1130.55  5596.8 1124.39  5782.5 1121.67  6252.4 1131.12
#Mann= 3 ,-1 , 0
  4176.8     .05       0  4956.9     .03       0  5053.3     .05       0
Bank Sta=4956.9,5053.3
XS Rating Curve= 0 ,0
Exp/Cntr=0.3,0.1

Type RM Length L Ch R = 1 ,4500    ,410,410,410
BEGIN DESCRIPTION:
HICKORY CREEK 9.0
END DESCRIPTION:
XS GIS Cut Line= 4
      2770419.58     10226359.34       2771384.3     10226255.42
      2771643.65     10225984.62      2772270.71     10225218.22
#Sta/Elev= 30
  4029.7 1125.84  4096.2 1124.43  4126.4 1127.45  4132.9  1124.8  4387.9 1118.71
  4428.1  1114.9  4659.4 1106.04  4749.9 1094.96  4770.1 1091.13  4860.6 1089.45
  4878.6 1087.78    4931 1090.22    4941 1090.02    4950 1087.63  4951.5 1086.43
  5044.9 1086.43  5046.4 1087.63  5052.1 1093.04  5059.1  1093.8  5136.4 1095.15
  5200.6 1101.08  5329.9 1109.12  5402.3 1111.99  5490.1 1112.65  5524.9 1112.67
    5627 1117.14  5761.6  1121.1  5895.8 1119.67    5974 1120.65  6365.2 1131.61
#Mann= 9 ,-1 , 0
  4029.7     .05       0    4950     .03       0  5046.4     .05       0
  5136.4     .12       0  5329.9     .05       0  5402.3     .12       0
  5490.1     .05       0  5524.9     .12       0    5627     .05       0
Bank Sta=4950,5046.4
XS Rating Curve= 0 ,0
Exp/Cntr=0.3,0.1

Type RM Length L Ch R = 1 ,4090    ,152,152,152
BEGIN DESCRIPTION:
Mapping XS 24d7560c
END DESCRIPTION:
XS GIS Cut Line= 6
       2770371.4     10226373.84      2770920.29     10226644.06
      2771224.29     10226673.61      2771481.85     10226648.28
       2771946.3     10226584.95       2772632.6       10226606.
#Sta/Elev= 30
    3907 1125.83  4276.5 1117.03  4501.1  1105.9  4614.6 1103.32  4624.7 1105.48
  4634.7 1102.16  4661.9 1099.74  4788.9 1097.86  4835.7 1096.35  4875.6 1088.61
  4948.3 1086.76  4949.8 1085.56  5044.7 1086.76  5046.7 1088.39    5097 1087.85
  5109.5 1090.34  5298.8 1101.72    5319 1106.54  5349.3 1101.31  5377.4 1101.08
  5389.7 1098.43  5440.1 1103.54  5488.6 1105.21  5588.3 1109.74    5687 1113.65
  5761.3 1115.83  5811.3  1123.3  5861.3 1122.47  6031.4 1129.46  6238.4 1132.97
#Mann= 8 ,-1 , 0
    3907     .05       0  4788.9    .075       0  4948.3     .07       0
  5044.7    .075       0  5109.5     .12       0  5488.6     .05       0
  5588.3     .12       0    5687     .05       0
Bank Sta=4948.3,5044.7
XS Rating Curve= 0 ,0
Exp/Cntr=0.3,0.1

Type RM Length L Ch R = 1 ,3938    ,438,438,438
BEGIN DESCRIPTION:
Mapping XS ce786d83
END DESCRIPTION:
XS GIS Cut Line= 6
       2770202.5     10226551.17      2770726.06     10226774.95
      2771101.84     10226834.06      2771600.07     10226791.84
      2771988.53     10226808.73      2772401.49     10226926.72
#Sta/Elev= 30
  3744.7 1126.76  3839.6 1121.92  3854.7 1122.36  3868.8 1121.27  4244.4 1111.48
  4336.7 1111.63  4344.1 1110.08  4394.2 1108.59  4748.5 1103.61  4838.9 1098.52
    4889 1088.87  4940.3 1087.56  4948.2 1086.16  4949.7 1084.96  5043.2 1084.96
  5044.7 1086.16  5049.6 1087.91  5073.7 1087.24    5150 1087.76    5170 1093.23
  5180.1 1094.32  5240.1 1095.18  5271.9 1097.25  5310.2 1100.76  5430.3 1105.23
  5540.4 1112.05  5801.7 1122.08  5981.1 1126.09  5986.3 1124.98  6012.8 1127.76
#Mann= 7 ,-1 , 0
  3744.7     .05       0  3854.7     .12       0  3868.8     .05       0
  4948.2     .03       0  5044.7     .05       0  5073.7    .075       0
  5271.9     .05       0
Bank Sta=4948.2,5044.7
XS Rating Curve= 0 ,0
Exp/Cntr=0.3,0.1

Type RM Length L Ch R = 1 ,3500    ,500,500,500
BEGIN DESCRIPTION:
HICKORY CREEK 7.0
END DESCRIPTION:
XS GIS Cut Line= 4
       2770780.7     10227278.12      2771205.82     10227349.54
      2771488.64     10227235.56      2772152.01     10226989.31
#Sta/Elev= 30
    4264 1123.23  4380.1 1121.18  4385.2 1122.07  4603.7 1110.73  4664.5 1110.75
  4716.5 1107.02  4747.9 1107.35  4831.2 1104.65  4878.2 1099.33    4909 1093.88
  4921.3  1093.3    4927 1084.34  4928.5 1083.14    5022 1083.14  5023.5 1084.34
  5052.8 1085.59  5077.9 1084.94  5108.2  1086.9  5124.8 1084.88  5163.6  1085.5
  5199.5    1093  5258.4 1095.92  5316.9 1100.38  5398.1 1101.91  5451.3 1105.66
    5512 1107.91  5537.1 1107.66  5562.1 1110.66  5592.5 1110.55  5707.6 1117.88
#Mann= 5 ,-1 , 0
    4264     .05       0    4927     .03       0  5023.5     .05       0
  5258.4     .12       0  5398.1     .05       0
Bank Sta=4927,5023.5
XS Rating Curve= 0 ,0
Exp/Cntr=0.3,0.1

Type RM Length L Ch R = 1 ,3000    ,500,500,500
BEGIN DESCRIPTION:
HICKORY CREEK 6.0
END DESCRIPTION:
XS GIS Cut Line= 5
      2771104.04     10227593.36      2771423.82     10227778.24
      2771778.05     10227635.19      2772357.87     10227332.82
        2772737.     10226944.83
#Sta/Elev= 30
  4248.6 1118.13  4394.9 1115.47  4452.6 1113.91  4618.3 1110.85  4723.8 1106.52
    4807 1098.88  4860.7 1091.26  4890.2  1084.1  4938.5    1085  4943.9 1083.05
  4945.4 1081.85  5040.4 1083.05  5053.3 1083.46  5081.1  1089.8  5177.8 1098.32
  5362.6 1105.63  5561.4 1107.43    5600 1111.48  5628.9 1109.55  5708.8 1112.63
  5758.2 1111.91  5963.3 1118.75  6012.9 1124.75  6076.4 1127.39  6111.9 1134.37
  6118.9 1132.26    6126 1134.88  6147.1 1134.35  6168.4 1140.05  6196.4 1133.68
#Mann= 7 ,-1 , 0
  4248.6     .05       0  4394.9     .05       0  4452.6     .05       0
  4618.3     .05       0  4860.7     .03       0  5081.1     .05       0
  5362.6     .05       0
Bank Sta=4943.9,5040.4
XS Rating Curve= 0 ,0
Exp/Cntr=0.3,0.1