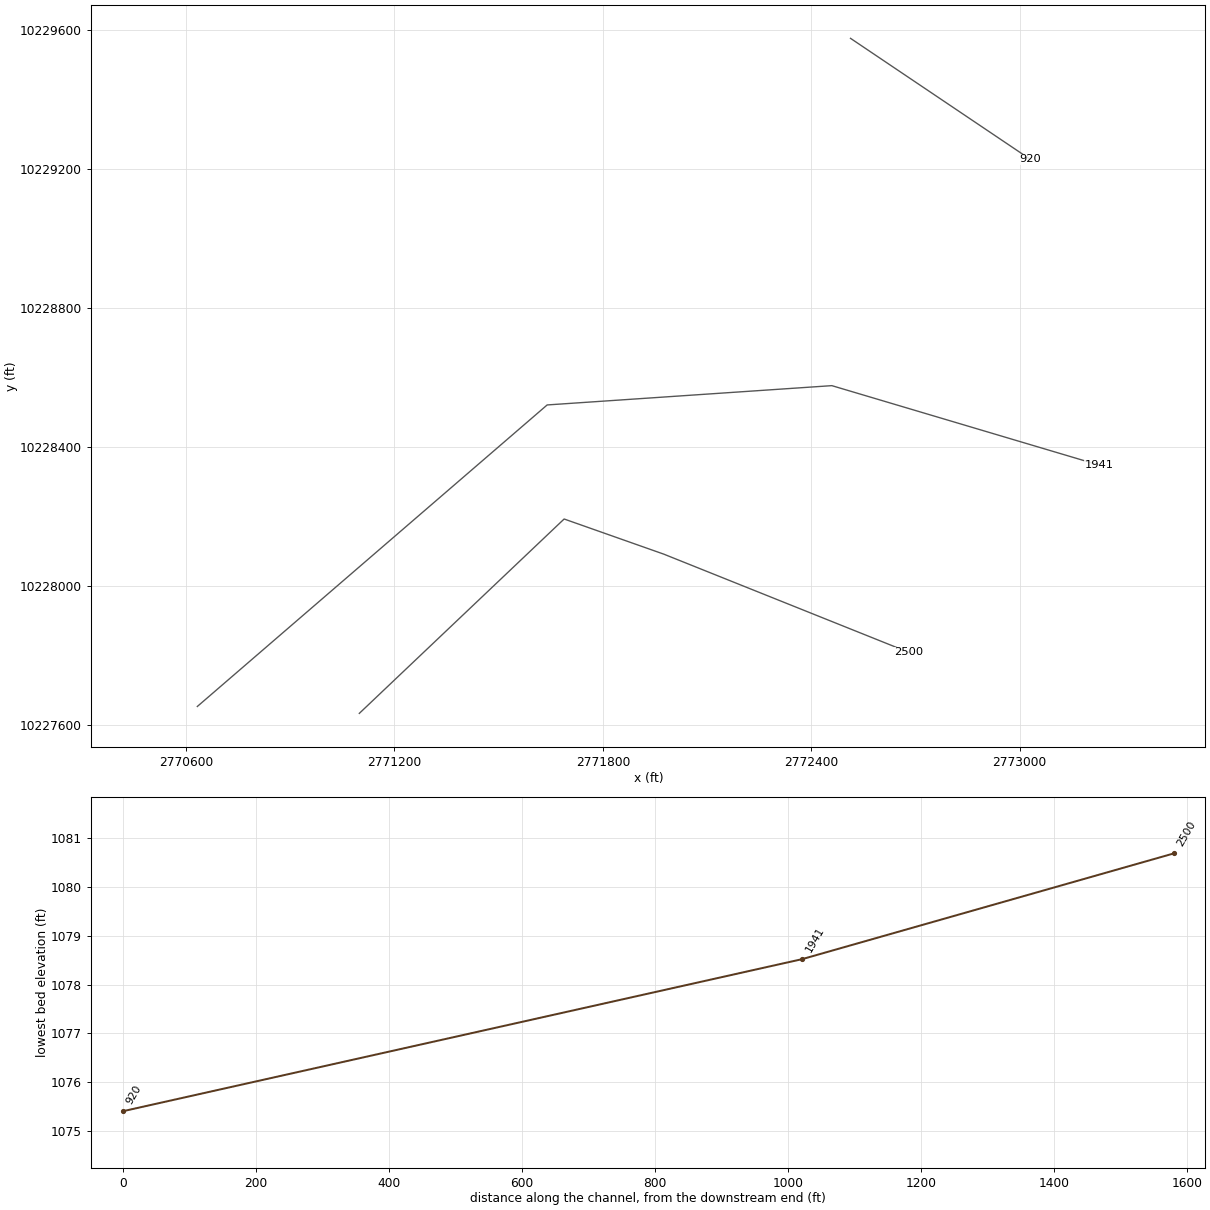
HEC-RAS study HICKORY CREEK.prj: HICKORY CREEK Base Level Engineering

--- HICKORY CREEK.g01 (geometry) --- (continued)

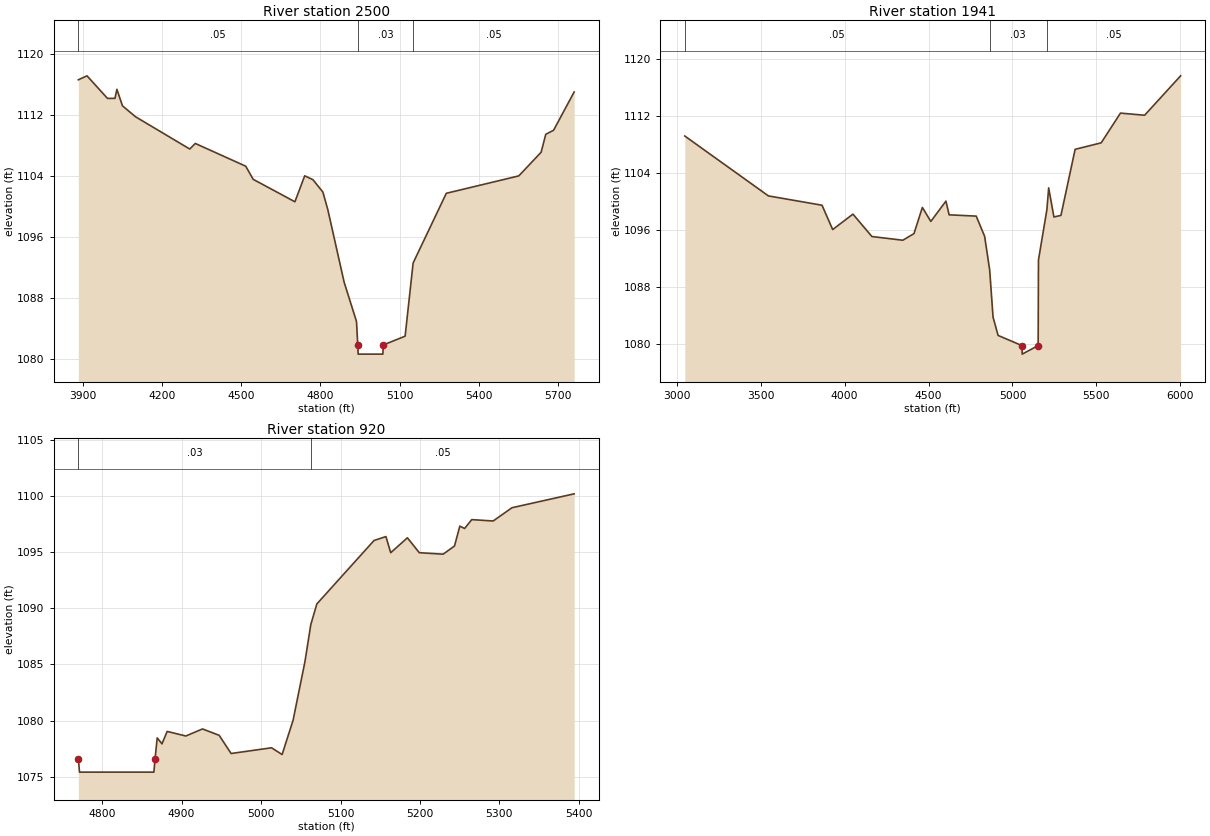
Type RM Length L Ch R = 1 ,2500    ,559,559,559
BEGIN DESCRIPTION:
HICKORY CREEK 5.0
END DESCRIPTION:
XS GIS Cut Line= 4
      2771099.09     10227633.37      2771688.62     10228192.92
      2771975.41     10228091.76      2772681.78     10227808.64
#Sta/Elev= 30
  3883.1 1116.63    3916 1117.15  3993.6 1114.19  4021.9  1114.2  4029.2 1115.38
  4050.3 1113.22  4099.6 1111.79  4305.1 1107.56  4326.1 1108.29  4517.1 1105.31
  4545.4 1103.59  4703.4 1100.65  4740.5 1104.05  4771.4 1103.55  4809.4 1101.92
    4828 1099.62  4889.8 1090.12  4936.7 1084.96  4941.4 1081.89  4942.9 1080.69
  5036.5 1080.69    5038 1081.89  5120.8 1083.04  5151.1 1092.63  5276.8 1101.76
  5551.3 1104.04  5635.9 1107.14  5653.5 1109.49  5683.1 1110.02    5761 1115.03
#Mann= 3 ,-1 , 0
  3883.1     .05       0  4941.4     .03       0  5151.1     .05       0
Bank Sta=4941.4,5038
XS Rating Curve= 0 ,0
Exp/Cntr=0.3,0.1

Type RM Length L Ch R = 1 ,1941    ,1021,1021,1021
BEGIN DESCRIPTION:
Mapping XS b604d1f7
END DESCRIPTION:
XS GIS Cut Line= 4
      2770632.84     10227653.22      2771639.75     10228521.25
      2772459.19      10228576.8      2773229.24     10228347.87
#Sta/Elev= 30
  3047.7 1109.18  3545.9 1100.76  3865.2 1099.45  3928.8 1096.03  4049.5  1098.2
  4162.5 1095.05  4346.8 1094.53  4413.1 1095.46  4463.2 1099.14  4513.4 1097.17
  4603.6 1100.03  4622.5  1098.1    4784 1097.92  4834.1 1095.08  4864.2 1090.35
  4884.2 1083.73  4914.3 1081.15  5056.4 1079.72  5057.9 1078.52    5153 1079.72
  5154.8 1091.74  5205.2 1098.85  5215.6 1101.89  5246.9  1097.8  5288.7 1098.02
  5373.3 1107.31  5528.6 1108.22  5643.4  1112.4  5787.3  1112.1  6001.8 1117.64
#Mann= 3 ,-1 , 0
  3047.7     .05       0  4864.2     .03       0  5205.2     .05       0
Bank Sta=5056.4,5153
XS Rating Curve= 0 ,0
Exp/Cntr=0.3,0.1

Type RM Length L Ch R = 1 ,920     ,0,0,0
BEGIN DESCRIPTION:
HICKORY CREEK 4.0
END DESCRIPTION:
XS GIS Cut Line= 2
      2772512.91     10229576.61      2773030.66     10229228.13
#Sta/Elev= 30
    4770  1076.6  4771.5  1075.4  4865.1  1075.4  4866.6  1076.6  4869.3 1078.45
  4875.3 1077.92  4881.8 1079.03  4905.3 1078.62  4926.3 1079.25  4947.3 1078.68
  4962.3 1077.06  5013.2 1077.57  5026.5 1076.97  5040.3 1080.02  5055.2 1085.23
  5062.6 1088.55  5070.2 1090.39  5142.2 1096.05  5157.2  1096.4  5163.2 1094.96
  5184.2 1096.29  5199.2 1094.96  5229.2 1094.83  5243.5 1095.56  5250.2 1097.33
  5256.2 1097.12  5265.2 1097.91  5292.2 1097.79  5315.8 1098.97  5394.1 1100.21
#Mann= 2 ,-1 , 0
    4770     .03       0  5062.6     .05       0
Bank Sta=4770,4866.6
XS Rating Curve= 0 ,0
Exp/Cntr=0.3,0.1

Chan Stop Cuts=-1
Use User Specified Reach Order=0
Composite Channel Slope=5