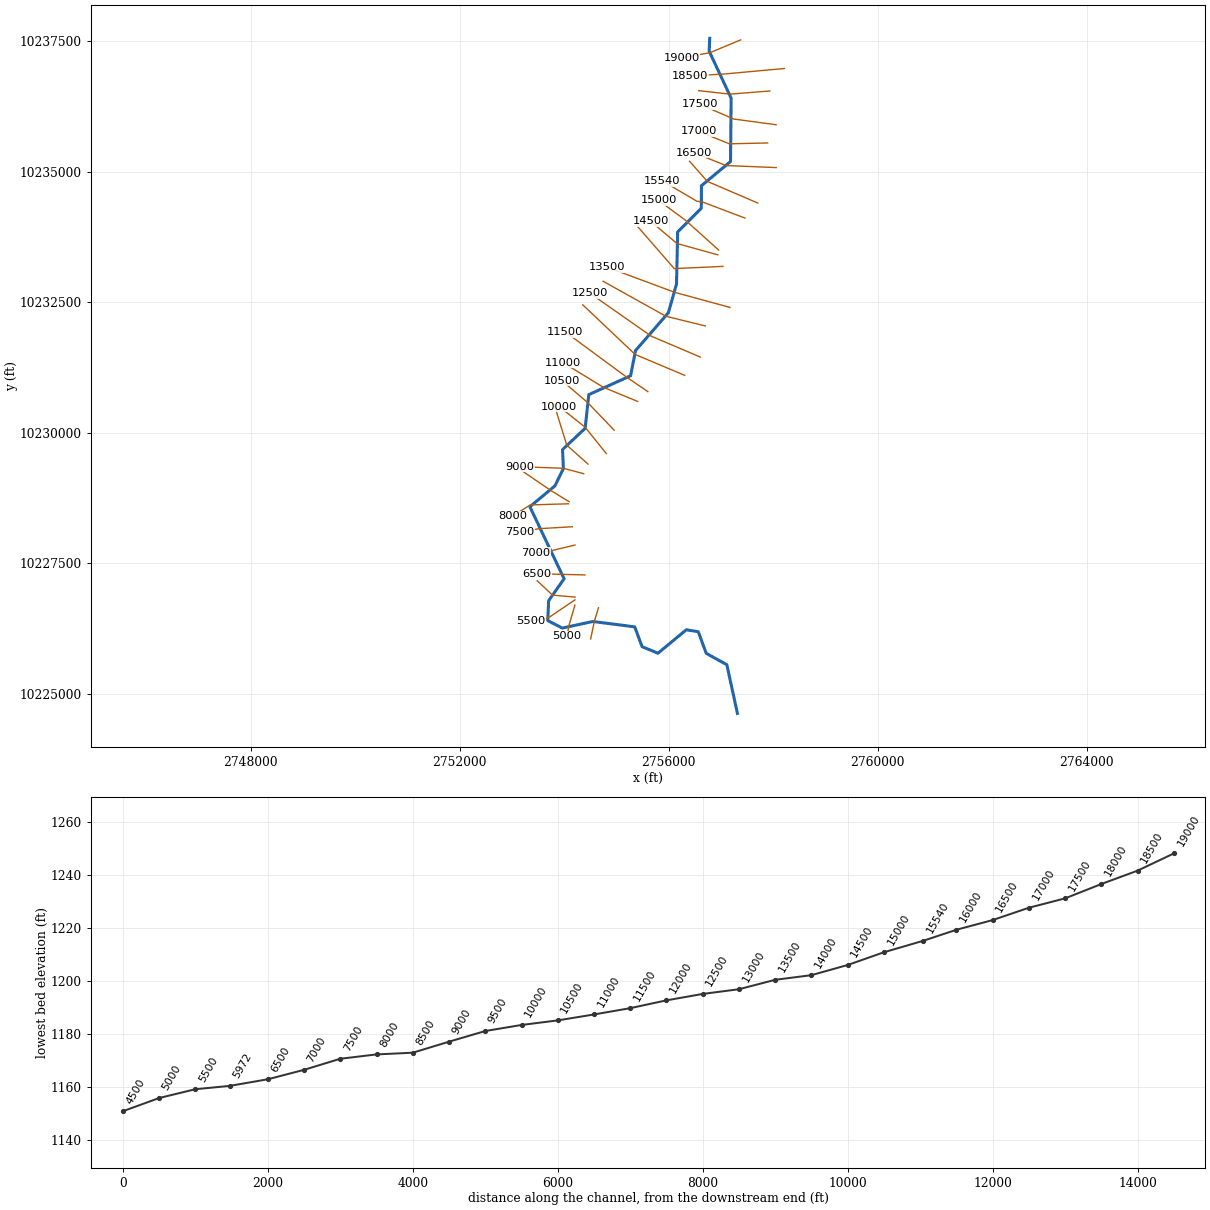
--- HICKORY01.prj (project) ---

Proj Title=HICKORY01 Base Level Engineering
Current Plan=p01
Default Exp/Contr=0.3,0.1
English Units
Geom File=g01
Flow File=f01
Plan File=p01
Y Axis Title=Elevation
X Axis Title(PF)=Main Channel Distance
X Axis Title(XS)=Station
BEGIN DESCRIPTION:
HICKORY01
END DESCRIPTION:
DSS Export Rating Curves= 0
DSS Export Rating Curve Sorted= 0
DSS Export Volume Flow Curves= 0
DXF OffsetX= 0
DXF OffsetY= 0
DXF ScaleX= 1
DXF ScaleY= 10

--- HICKORY01.p01 (plan) ---

Plan Title=Multiple Run
Short Identifier=Multiple
Geom File=g01
Flow File=f01
Subcritical Flow
K Sum by GR= 0
Std Step Tol= 0.01
Critical Tol= 0.01
Num of Std Step Trials= 20
Max Error Tol= 0.3
Flow Tol Ratio= 0.001
Split Flow NTrial= 30
Split Flow Tol= 0.02
Split Flow Ratio= 0.02
Log Output Level= 0
Friction Slope Method= 1
Unsteady Friction Slope Method= 2
Unsteady Bridges Friction Slope Method= 1
Parabolic Critical Depth
Global Vel Dist=  1 , 1 , 1
Global Log Level= 0
CheckData=True
Encroach Param= -1, 0, 0, 0
BEGIN DESCRIPTION:
Multiple Run
END DESCRIPTION:

--- HICKORY01.f01 (steady flow) ---

Flow Title=Multiple
Number of Profiles=7
Profile Names=10-year,25-year,50-year,1pct_min,100-year,1pct_plu,500-year
River Rch & RM= HICKORY01,Reach-1,19000
     379     605     739     569     966    1640    1304
River Rch & RM= HICKORY01,Reach-1,13500
     564     928    1070     761    1410    2612    1895
River Rch & RM= HICKORY01,Reach-1,9000
    1171    2021    2648    1828    3614    7148    4879
Boundary for River Rch & Prof#=HICKORY01,Reach-1,1
Up Type=0
Dn Type=3
Dn Slope=0.005
Boundary for River Rch & Prof#=HICKORY01,Reach-1,2
Up Type=0
Dn Type=3
Dn Slope=0.005
Boundary for River Rch & Prof#=HICKORY01,Reach-1,3
Up Type=0
Dn Type=3
Dn Slope=0.005
Boundary for River Rch & Prof#=HICKORY01,Reach-1,4
Up Type=0
Dn Type=3
Dn Slope=0.005
Boundary for River Rch & Prof#=HICKORY01,Reach-1,5
Up Type=0
Dn Type=3
Dn Slope=0.005
Boundary for River Rch & Prof#=HICKORY01,Reach-1,6
Up Type=0
Dn Type=3
Dn Slope=0.005
Boundary for River Rch & Prof#=HICKORY01,Reach-1,7
Up Type=0
Dn Type=3
Dn Slope=0.005

--- HICKORY01.g01 (geometry) ---

Geom Title=Existing Conditions
Program Version=4.10

River Reach=HICKORY01       ,Reach-1
Reach XY= 30
       2756784.5       10237558.      2756774.25       10237311.
       2757194.5       10236413.        2757183.       10235199.
      2756625.75       10234734.       2756623.5       10234303.
      2756171.25       10233850.      2756149.25       10232854.
        2755993.       10232302.        2755364.       10231577.
      2755270.25       10231095.      2754470.75       10230734.
        2754400.       10230089.       2753967.5       10229681.
      2753984.25       10229318.        2753822.       10228986.
      2753342.75       10228587.       2753997.5       10227207.
      2753701.25       10226786.      2753685.75       10226405.
        2753963.       10226263.      2754549.25       10226389.
      2755349.25       10226286.       2755489.5       10225907.
       2755793.5       10225781.      2756336.75       10226230.
       2756565.5       10226193.      2756717.75       10225779.
      2757112.25       10225561.      2757314.75       10224629.

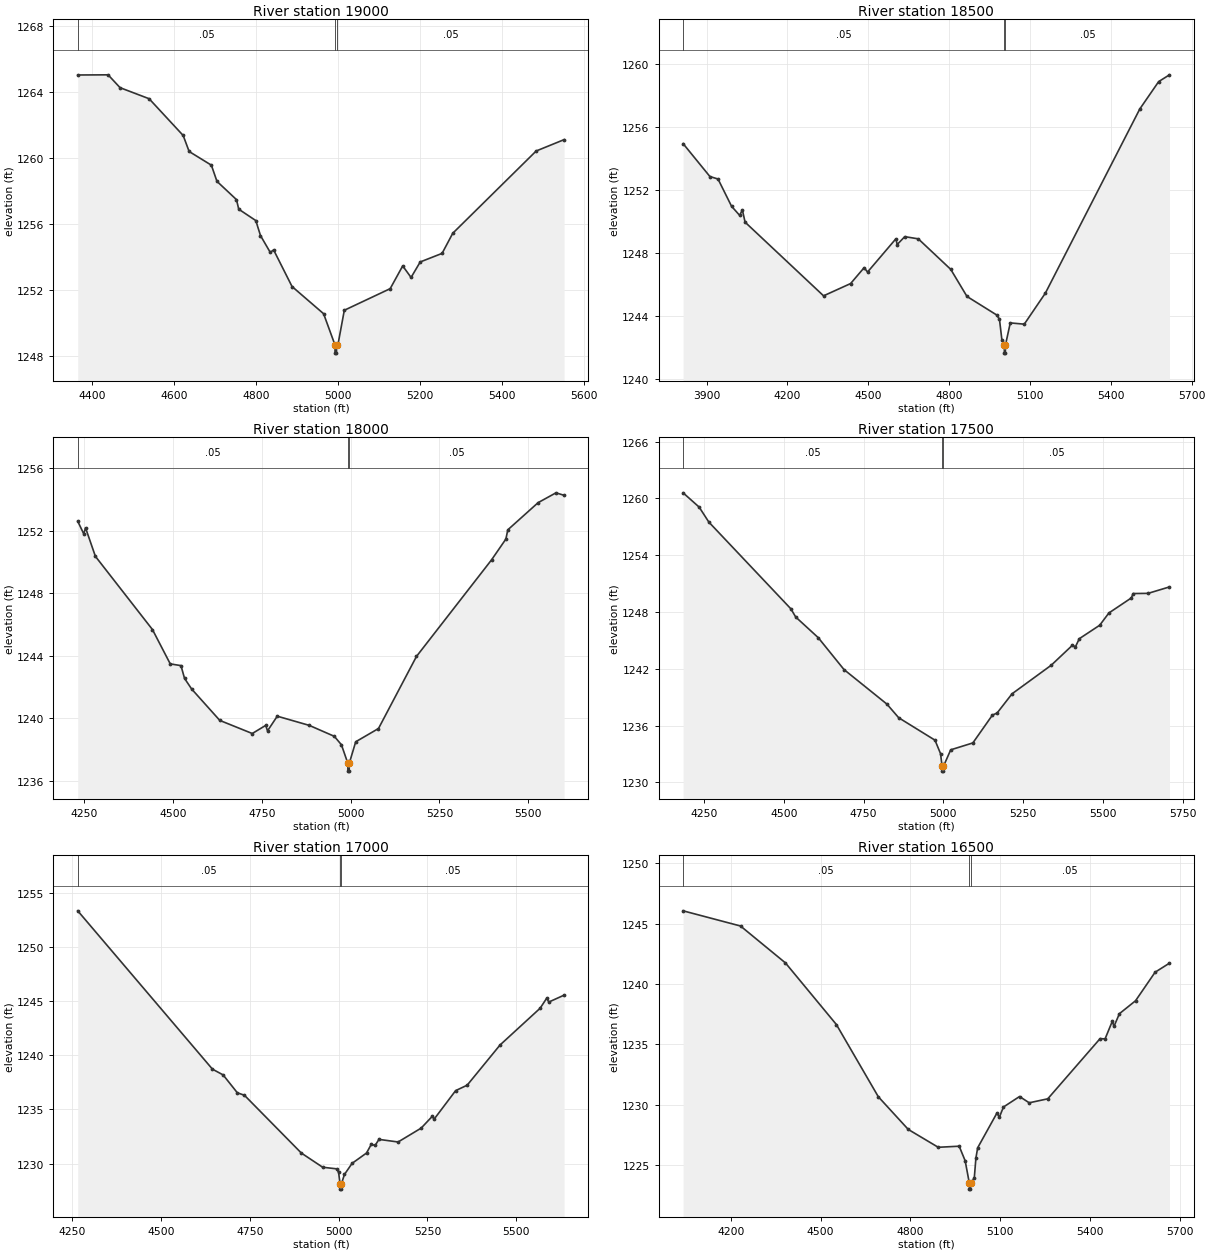
Type RM Length L Ch R = 1 ,19000   ,500,500,500
BEGIN DESCRIPTION:
HICKORY01 38.0
END DESCRIPTION:
XS GIS Cut Line= 3
      2757376.27      10237527.7      2756791.04     10237283.61
      2756248.71     10237184.56
#Sta/Elev= 30
  4365.9 1265.03  4439.9 1265.04  4469.1 1264.26  4539.9 1263.59  4622.9 1261.36
  4637.4 1260.39  4691.6 1259.56  4705.2 1258.58  4752.8 1257.47  4758.3 1256.89
  4799.9  1256.2  4811.3 1255.29  4835.1 1254.27  4843.3 1254.42  4888.2  1252.2
  4965.1 1250.55  4992.8 1248.66    4993 1248.16  4996.5 1248.16  4996.8 1248.66
    5000 1248.66  5015.6 1250.76  5127.4 1252.07  5157.9 1253.45  5178.3 1252.75
  5200.6 1253.69  5253.9 1254.21  5279.9 1255.43  5483.2 1260.42  5551.3 1261.11
#Mann= 3 ,-1 , 0
  4365.9     .05       0  4992.8     .03       0  4996.8     .05       0
Bank Sta=4992.8,4996.8
XS Rating Curve= 0 ,0
Exp/Cntr=0.3,0.1

Type RM Length L Ch R = 1 ,18500   ,500,500,500
BEGIN DESCRIPTION:
HICKORY01 37.0
END DESCRIPTION:
XS GIS Cut Line= 3
       2758214.7     10236980.44      2757032.57     10236871.95
      2756415.66     10236840.71
#Sta/Elev= 30
  3812.9 1254.97  3912.3 1252.88  3942.5 1252.72  3992.7 1250.99  4022.8 1250.41
  4032.8 1250.76  4042.9 1249.98  4334.1  1245.3  4434.5 1246.08  4484.7 1247.09
  4497.3 1246.81  4602.3 1248.92  4607.3 1248.56  4635.4 1249.06  4685.6 1248.92
  4806.1 1246.98  4866.3 1245.26  4976.8 1244.08  4986.8 1243.81  4995.9 1242.49
  5004.9 1242.16  5005.1 1241.66  5008.6 1241.66  5008.9 1242.16  5026.9 1243.58
  5078.9  1243.5  5157.1 1245.47  5507.5 1257.17  5577.6 1258.91  5617.7 1259.34
#Mann= 3 ,-1 , 0
  3812.9     .05       0  5004.9     .03       0  5008.9     .05       0
Bank Sta=5004.9,5008.9
XS Rating Curve= 0 ,0
Exp/Cntr=0.3,0.1

Type RM Length L Ch R = 1 ,18000   ,500,500,500
BEGIN DESCRIPTION:
HICKORY01 36.0
END DESCRIPTION:
XS GIS Cut Line= 3
      2757935.24     10236549.61      2757169.88     10236489.67
      2756572.89     10236555.42
#Sta/Elev= 30
  4232.3 1252.62  4249.2 1251.81  4254.2  1252.2    4282 1250.37  4442.5 1245.68
  4492.6 1243.48  4522.7 1243.37  4532.8 1242.55  4552.8 1241.87  4631.9 1239.86
  4723.3 1239.02  4761.1 1239.54  4766.2 1239.19  4793.6 1240.13  4883.8 1239.54
  4954.1 1238.84  4974.1  1238.3  4992.2 1237.11  4992.4 1236.61  4995.9 1236.61
  4996.2 1237.11  5014.3 1238.49  5078.4 1239.34  5185.3 1243.96  5396.6 1250.15
  5436.8 1251.48  5442.2 1252.07  5527.4 1253.81  5577.7 1254.44  5600.6 1254.28
#Mann= 3 ,-1 , 0
  4232.3     .05       0  4992.2     .03       0  4996.2     .05       0
Bank Sta=4992.2,4996.2
XS Rating Curve= 0 ,0
Exp/Cntr=0.3,0.1

Type RM Length L Ch R = 1 ,17500   ,500,500,500
BEGIN DESCRIPTION:
HICKORY01 35.0
END DESCRIPTION:
XS GIS Cut Line= 3
      2758055.64     10235903.12      2757246.72     10236011.92
      2756596.12     10236293.44
#Sta/Elev= 30
  4183.8 1260.59  4234.2 1259.08  4264.5  1257.5  4521.6 1248.34  4536.9 1247.47
  4607.5 1245.29  4688.3 1241.92  4822.9 1238.27  4859.8 1236.83  4973.6 1234.46
    4991 1233.04    4996 1231.69  4996.3 1231.19  4999.8 1231.19    5000 1231.69
  5022.9 1233.44  5092.4 1234.17  5153.7 1237.11  5168.4 1237.33  5215.3 1239.36
  5338.2 1242.38  5404.3 1244.48  5414.1 1244.33  5426.1 1245.18    5490  1246.6
    5519  1247.9  5589.4 1249.49  5594.9 1249.95  5641.8 1249.97  5708.9 1250.65
#Mann= 3 ,-1 , 0
  4183.8     .05       0    4996     .03       0    5000     .05       0
Bank Sta=4996,5000
XS Rating Curve= 0 ,0
Exp/Cntr=0.3,0.1

Type RM Length L Ch R = 1 ,17000   ,500,500,500
BEGIN DESCRIPTION:
HICKORY01 34.0
END DESCRIPTION:
XS GIS Cut Line= 3
      2757894.45     10235554.03      2757160.93     10235537.66
      2756572.82     10235775.28
#Sta/Elev= 30
  4266.3 1253.33  4645.2 1238.72  4675.2 1238.19  4715.2 1236.54  4735.2 1236.31
  4895.2 1230.98  4955.2 1229.67  4995.1 1229.52    5000 1229.19  5004.1 1228.15
  5004.4 1227.65  5007.9 1227.65  5008.1 1228.15  5016.4    1229    5038 1230.03
  5078.5 1230.98  5091.9 1231.78  5102.7 1231.68  5113.5 1232.24  5167.4    1232
  5232.2 1233.28  5263.6 1234.37    5269 1234.12  5329.2 1236.74  5361.6 1237.24
  5454.1 1240.95  5566.8 1244.34  5585.6 1245.28    5591 1244.91  5634.3 1245.55
#Mann= 3 ,-1 , 0
  4266.3     .05       0  5004.1     .05       0  5008.1     .05       0
Bank Sta=5004.1,5008.1
XS Rating Curve= 0 ,0
Exp/Cntr=0.3,0.1

Type RM Length L Ch R = 1 ,16500   ,500,500,500
BEGIN DESCRIPTION:
HICKORY01 33.0
END DESCRIPTION:
XS GIS Cut Line= 3
      2758057.44     10235082.45      2757098.93     10235121.26
      2756480.23     10235367.51
#Sta/Elev= 30
  4040.7 1246.07  4232.6 1244.81  4382.7 1241.75  4552.9 1236.64    4693 1230.65
  4793.1 1227.94  4893.2 1226.46  4963.2 1226.55  4983.2 1225.34  4997.1 1223.49
  4997.4 1222.99  5000.9 1222.99  5001.1 1223.49  5013.7 1223.92  5019.1 1225.57
    5025 1226.42  5089.6 1229.31  5097.3 1228.94  5111.1  1229.8  5164.9 1230.67
  5197.2 1230.15  5259.2 1230.48    5434 1235.47  5450.7 1235.45    5475 1236.92
  5480.3 1236.48  5498.6 1237.54  5552.4 1238.61  5617.9 1240.98  5665.9 1241.73
#Mann= 3 ,-1 , 0
  4040.7     .05       0  4997.1     .03       0  5001.1     .05       0
Bank Sta=4997.1,5001.1
XS Rating Curve= 0 ,0
Exp/Cntr=0.3,0.1

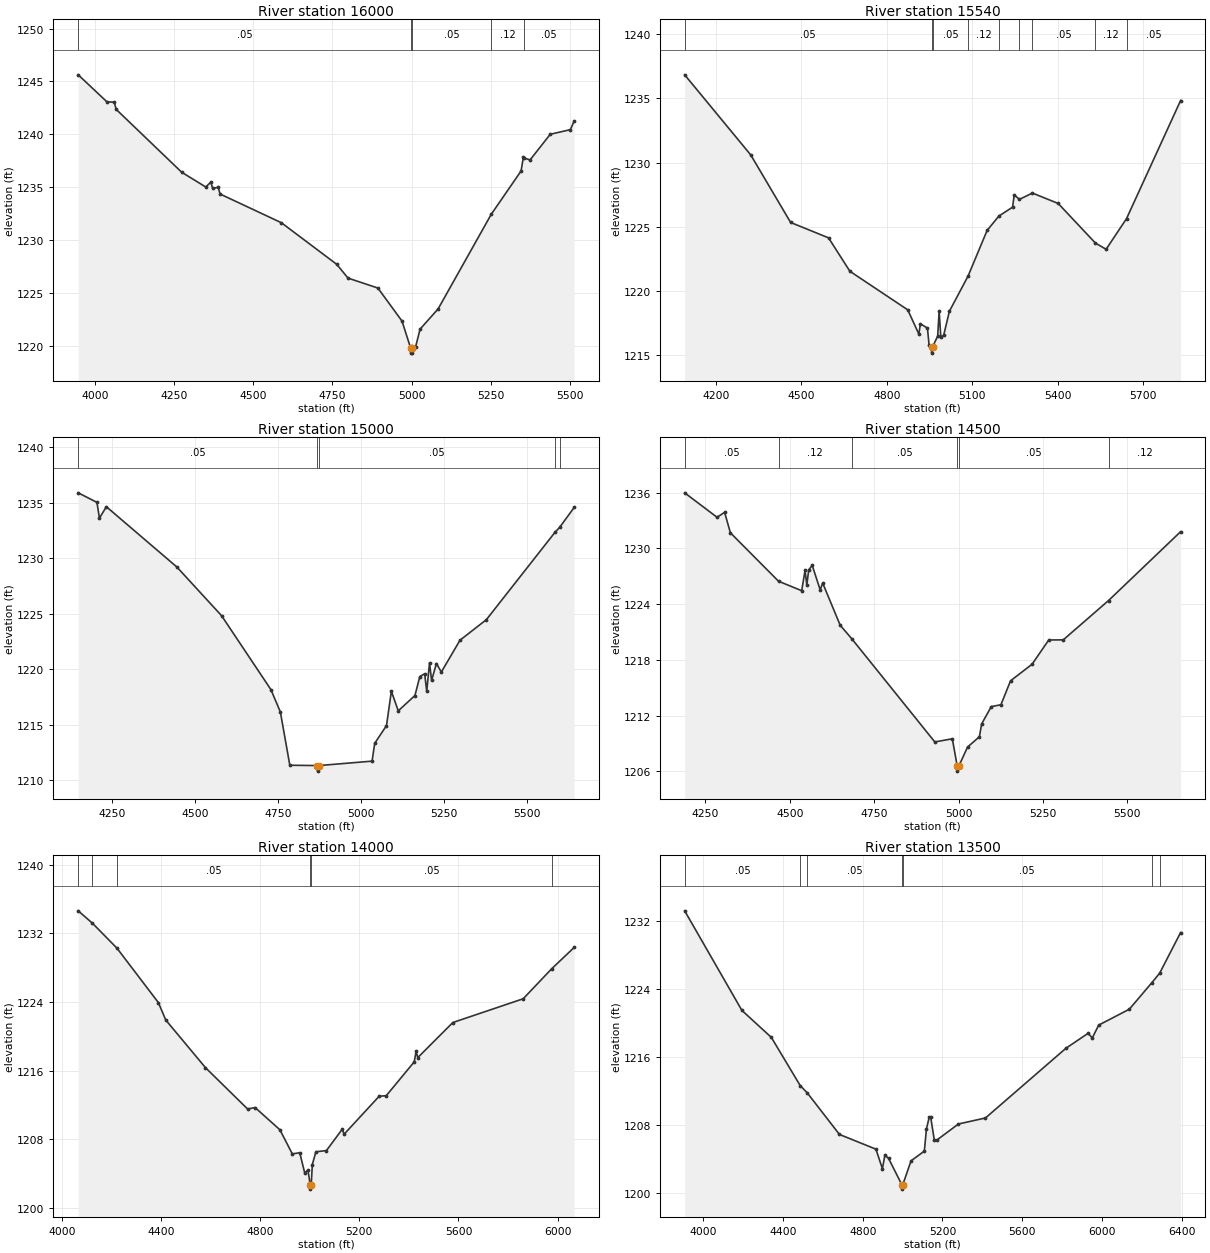
Type RM Length L Ch R = 1 ,16000   ,460,460,460
BEGIN DESCRIPTION:
HICKORY01 32.0
END DESCRIPTION:
XS GIS Cut Line= 3
      2757705.66     10234403.12      2756738.68      10234818.2
      2756399.44     10235203.28
#Sta/Elev= 30
  3947.7 1245.63  4038.3 1243.08  4061.8 1243.04  4067.4 1242.37  4274.1 1236.43
  4350.3 1235.03  4366.3 1235.49  4372.1 1234.89  4389.9 1235.01  4395.3 1234.37
  4589.2 1231.65  4763.8 1227.72  4799.4 1226.42  4893.7 1225.48  4969.8 1222.36
  4996.8 1219.83    4997 1219.33  5000.5 1219.33  5000.8 1219.83  5012.7 1219.92
  5026.9  1221.6  5083.8 1223.51  5251.7 1232.46  5345.6 1236.54    5353 1237.86
  5355.1 1237.77  5374.1 1237.59  5437.7 1240.01  5501.2 1240.45  5513.2 1241.26
#Mann= 5 ,-1 , 0
  3947.7     .05       0  4996.8     .05       0  5000.8     .05       0
  5251.7     .12       0  5355.1     .05       0
Bank Sta=4996.8,5000.8
XS Rating Curve= 0 ,0
Exp/Cntr=0.3,0.1

Type RM Length L Ch R = 1 ,15540   ,540,540,540
BEGIN DESCRIPTION:
HICKORY01 31.0
END DESCRIPTION:
XS GIS Cut Line= 4
      2757457.81     10234115.98      2756640.77     10234425.96
      2756540.07     10234437.81      2755880.32      10234826.1
#Sta/Elev= 30
  4090.2 1236.83  4322.1 1230.59  4462.1 1225.33  4595.2 1224.13    4670 1221.53
  4873.3 1218.52  4912.2 1216.63  4917.6 1217.43  4942.4  1217.1  4948.1 1215.77
  4956.8 1215.65    4957 1215.15  4960.8 1215.65  4978.3 1216.48  4983.4 1218.43
  4989.3 1216.39  4999.4 1216.55  5019.5 1218.42  5084.9 1221.15  5151.8 1224.71
  5193.2 1225.83  5241.1 1226.52    5247 1227.47  5265.4 1227.13  5310.8 1227.62
  5401.2 1226.81  5532.1 1223.72  5569.5 1223.24  5641.2 1225.63    5831 1234.83
#Mann= 9 ,-1 , 0
  4090.2     .05       0  4956.8     .03       0  4960.8     .05       0
  5084.9     .12       0  5193.2     .05       0  5265.4     .12       0
  5310.8     .05       0  5532.1     .12       0  5641.2     .05       0
Bank Sta=4956.8,4960.8
XS Rating Curve= 0 ,0
Exp/Cntr=0.3,0.1

Type RM Length L Ch R = 1 ,15000   ,500,500,500
BEGIN DESCRIPTION:
HICKORY01 30.0
END DESCRIPTION:
XS GIS Cut Line= 3
      2756955.66     10233503.14      2756322.92     10234072.37
      2755805.66     10234453.13
#Sta/Elev= 30
  4148.9  1235.9  4205.3 1235.04  4212.8 1233.62  4233.7 1234.65    4446 1229.22
  4580.5 1224.84  4729.2 1218.18  4757.7 1216.16  4786.1 1211.37  4869.3 1211.34
  4869.5 1210.84  4873.3 1211.34  5033.8 1211.74  5041.7 1213.34  5077.2 1214.94
  5091.9 1218.03  5112.7 1216.27  5162.9 1217.65  5177.5 1219.35  5192.1 1219.61
  5198.4 1218.03  5206.8 1220.59    5213 1219.01  5227.6 1220.53  5242.3 1219.76
  5298.6 1222.63    5378 1224.48  5584.2 1232.33  5598.8  1232.8  5642.3 1234.58
#Mann= 5 ,-1 , 0
  4148.9     .05       0  4869.3     .05       0  4873.3     .05       0
  5584.2     .12       0  5598.8     .05       0
Bank Sta=4869.3,4873.3
XS Rating Curve= 0 ,0
Exp/Cntr=0.3,0.1

Type RM Length L Ch R = 1 ,14500   ,500,500,500
BEGIN DESCRIPTION:
HICKORY01 29.0
END DESCRIPTION:
XS GIS Cut Line= 3
      2756939.64     10233411.51      2756157.85     10233628.31
      2755655.72     10234053.08
#Sta/Elev= 30
  4188.7 1235.97  4284.6 1233.34    4307 1233.87  4324.1 1231.67  4466.7 1226.46
  4535.3 1225.44  4545.3 1227.63  4550.5 1226.04    4556 1227.67  4566.4 1228.17
    4590 1225.54  4597.5 1226.26  4649.4 1221.72  4683.2 1220.29  4929.6 1209.17
  4981.5 1209.51  4996.2 1206.53  4996.4 1206.03  5000.2 1206.53  5026.6 1208.62
  5061.7 1209.73  5068.3 1211.11  5096.8 1212.97  5125.4 1213.17    5154 1215.75
  5217.7 1217.53  5267.1 1220.14    5310 1220.15  5444.1 1224.38  5657.7 1231.79
#Mann= 6 ,-1 , 0
  4188.7     .05       0  4466.7     .12       0  4683.2     .05       0
  4996.2     .05       0  5000.2     .05       0  5444.1     .12       0
Bank Sta=4996.2,5000.2
XS Rating Curve= 0 ,0
Exp/Cntr=0.3,0.1

Type RM Length L Ch R = 1 ,14000   ,500,500,500
BEGIN DESCRIPTION:
HICKORY01 28.0
END DESCRIPTION:
XS GIS Cut Line= 3
      2757038.61     10233190.28      2756105.28     10233147.71
       2755405.7     10233953.09
#Sta/Elev= 30
  4065.7 1234.63  4123.3 1233.18    4222 1230.28    4389 1223.94    4419  1221.9
  4579.2 1216.35  4749.3 1211.53  4779.4  1211.7  4879.5 1209.11  4929.5  1206.3
  4959.6 1206.43  4979.6 1204.08  4992.8 1204.41  5001.8 1202.69    5002 1202.19
  5005.8 1202.69  5010.4 1205.06  5024.6 1206.54  5067.4 1206.69    5131 1209.17
  5138.6 1208.59  5280.1 1213.02  5308.6 1213.08  5421.6 1217.03  5429.2 1218.27
  5435.8 1217.52  5577.3 1221.61  5861.2 1224.38  5975.9 1227.87  6066.8 1230.36
#Mann= 6 ,-1 , 0
  4065.7     .05       0  4123.3     .12       0    4222     .05       0
  5001.8     .05       0  5005.8     .05       0  5975.9     .12       0
Bank Sta=5001.8,5005.8
XS Rating Curve= 0 ,0
Exp/Cntr=0.3,0.1

Type RM Length L Ch R = 1 ,13500   ,500,500,500
BEGIN DESCRIPTION:
HICKORY01 27.0
END DESCRIPTION:
XS GIS Cut Line= 3
       2757172.5      10232404.3      2756117.83     10232692.35
      2754810.42     10233178.01
#Sta/Elev= 30
  3906.7 1233.17  4193.7 1221.46  4341.3 1218.29  4486.2 1212.62  4521.7 1211.76
  4683.2 1206.87  4866.2 1205.14  4898.6 1202.84  4911.1 1204.43  4929.7 1204.05
  4996.5 1200.94  4996.8 1200.44  5000.6 1200.94  5042.4 1203.77    5109 1204.91
  5119.6 1207.52  5133.5  1208.9    5141  1208.9  5158.6 1206.27    5173 1206.23
    5280  1208.1  5415.8 1208.81  5819.5 1217.01  5930.3 1218.76  5951.7 1218.23
  5983.7 1219.73  6137.5  1221.6  6250.4 1224.72  6289.4 1225.83  6394.7 1230.62
#Mann= 7 ,-1 , 0
  3906.7     .05       0  4486.2     .12       0  4521.7     .05       0
  4996.5     .03       0  5000.6     .05       0  6250.4     .12       0
  6289.4     .05       0
Bank Sta=4996.5,5000.6
XS Rating Curve= 0 ,0
Exp/Cntr=0.3,0.1

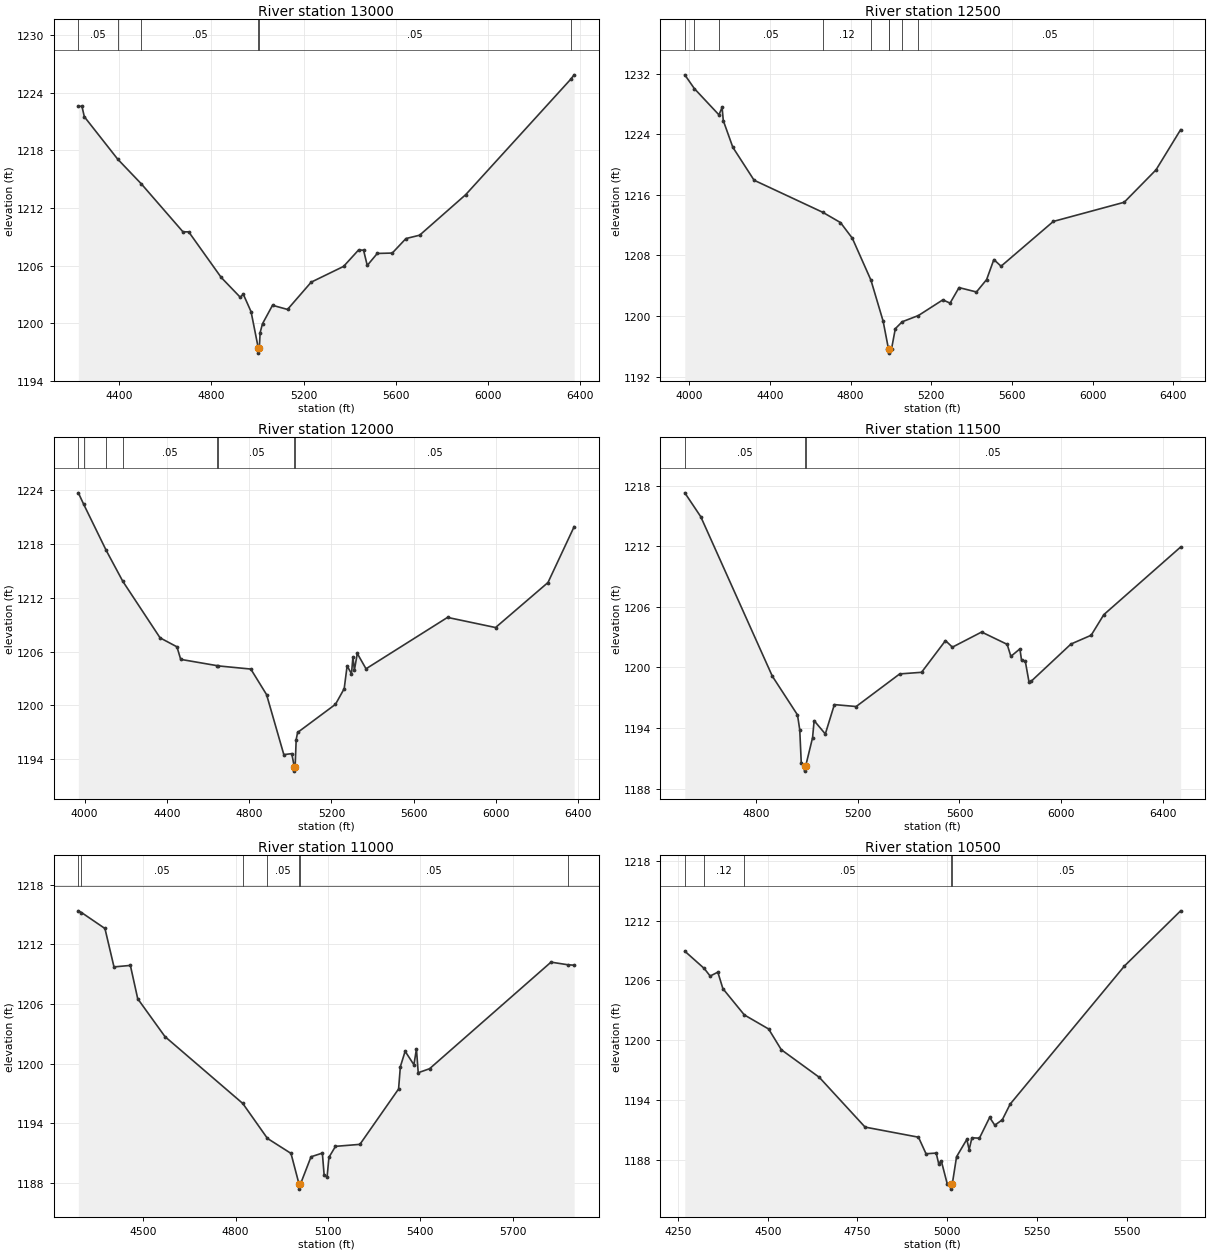
Type RM Length L Ch R = 1 ,13000   ,500,500,500
BEGIN DESCRIPTION:
HICKORY01 26.0
END DESCRIPTION:
XS GIS Cut Line= 3
      2756700.92     10232049.15      2755945.32     10232235.32
      2754744.75     10232904.98
#Sta/Elev= 30
  4221.8 1222.59  4237.5 1222.58  4247.8  1221.5  4392.7 1217.08  4495.5  1214.5
  4676.2 1209.51    4701 1209.51  4842.2 1204.76  4925.2 1202.69  4937.8 1203.03
  4971.9 1201.19  5003.4 1197.38  5003.7 1196.88  5007.6 1197.38  5011.2 1199.02
  5021.5 1199.94  5064.9 1201.86  5130.1 1201.43  5232.9 1204.27  5373.5 1205.91
  5438.6 1207.62  5460.3  1207.6  5476.3 1206.01  5519.8 1207.26  5584.9  1207.3
  5644.3 1208.81  5703.7 1209.16  5903.7 1213.38  6359.4 1225.39  6374.7 1225.86
#Mann= 6 ,-1 , 0
  4221.8     .05       0  4392.7     .12       0  4495.5     .05       0
  5003.4     .03       0  5007.6     .05       0  6359.4     .12       0
Bank Sta=5003.4,5007.6
XS Rating Curve= 0 ,0
Exp/Cntr=0.3,0.1

Type RM Length L Ch R = 1 ,12500   ,500,500,500
BEGIN DESCRIPTION:
HICKORY01 25.0
END DESCRIPTION:
XS GIS Cut Line= 3
      2756605.67     10231453.12      2755665.89     10231853.47
      2754489.63     10232677.18
#Sta/Elev= 30
  3978.5 1231.83    4026 1230.01  4147.7 1226.55  4163.3 1227.53  4169.3 1225.79
  4216.5 1222.27  4321.9 1217.92  4662.8 1213.68  4750.2 1212.33  4808.9 1210.26
    4901 1204.74  4961.5 1199.32  4988.4  1195.6  4988.7  1195.1  4992.7  1195.6
  5003.2 1195.66    5022 1198.33    5056 1199.24  5136.2 1200.06  5257.4 1202.13
  5293.3  1201.7  5337.7 1203.75    5424 1203.17  5474.5 1204.81  5510.3 1207.45
    5546 1206.57    5805 1212.48  6156.3 1215.01  6314.1 1219.29    6436 1224.59
#Mann= 9 ,-1 , 0
  3978.5     .05       0    4026     .12       0  4147.7     .05       0
  4662.8     .12       0    4901     .05       0  4988.4     .03       0
  4992.7     .05       0    5056     .12       0  5136.2     .05       0
Bank Sta=4988.4,4992.7
XS Rating Curve= 0 ,0
Exp/Cntr=0.3,0.1

Type RM Length L Ch R = 1 ,12000   ,500,500,500
BEGIN DESCRIPTION:
HICKORY01 24.0
END DESCRIPTION:
XS GIS Cut Line= 3
      2756305.67     10231103.12      2755356.67     10231503.99
       2754355.7      10232453.1
#Sta/Elev= 30
  3969.8 1223.71  3996.3 1222.41  4105.5 1217.28  4185.8 1213.85  4367.1 1207.54
    4449 1206.54  4467.3 1205.14    4644 1204.44  4650.8 1204.41    4808 1204.06
  4884.6 1201.21  4968.5 1194.52  5007.1 1194.63  5019.1 1193.18  5019.4 1192.68
  5023.4 1193.18  5028.5  1196.2  5035.4 1196.99  5219.5 1200.13  5261.9 1201.88
  5276.1 1204.42  5297.2 1203.53  5304.4 1205.42  5311.3 1203.93  5325.5  1205.8
  5367.9 1204.09    5764 1209.82  5997.4 1208.69  6252.2 1213.71  6379.4 1219.94
#Mann= 8 ,-1 , 0
  3969.8     .12       0  3996.3     .05       0  4105.5     .12       0
  4185.8     .05       0    4644     .12       0  4650.8     .05       0
  5019.1     .03       0  5023.4     .05       0
Bank Sta=5019.1,5023.4
XS Rating Curve= 0 ,0
Exp/Cntr=0.3,0.1

Type RM Length L Ch R = 1 ,11500   ,500,500,500
BEGIN DESCRIPTION:
HICKORY01 23.0
END DESCRIPTION:
XS GIS Cut Line= 3
      2755600.53     10230791.61      2755204.89     10231061.44
      2754022.78     10231932.71
#Sta/Elev= 30
  4521.1  1217.3  4583.7 1214.94  4864.8 1199.14  4963.7  1195.3  4972.6 1193.82
  4978.6 1190.49  4991.3 1190.23  4991.6 1189.73  4995.8 1190.23  5022.9 1193.04
  5029.1 1194.73    5073 1193.41  5108.5 1196.32  5194.1 1196.13  5365.2 1199.36
    5451 1199.52    5545 1202.66  5572.1 1202.01    5687 1203.51  5787.2 1202.29
  5801.8  1201.1  5837.3 1201.84  5843.8  1200.7  5858.2 1200.65  5872.8 1198.59
    5881 1198.62  6037.8 1202.32  6117.1 1203.19  6166.8 1205.23  6468.5 1211.93
#Mann= 3 ,-1 , 0
  4521.1     .05       0  4991.3     .03       0  4995.8     .05       0
Bank Sta=4991.3,4995.8
XS Rating Curve= 0 ,0
Exp/Cntr=0.3,0.1

Type RM Length L Ch R = 1 ,11000   ,500,500,500
BEGIN DESCRIPTION:
HICKORY01 22.0
END DESCRIPTION:
XS GIS Cut Line= 3
       2755405.7     10230603.11      2754748.73     10230874.46
      2753982.04     10231344.68
#Sta/Elev= 30
  4289.2 1215.39  4299.4 1215.22  4375.6 1213.61    4405 1209.74  4458.2 1209.89
  4482.1 1206.53  4570.5 1202.72  4823.3 1195.98  4903.3 1192.46  4979.8 1190.95
    5006 1187.85  5006.3 1187.35  5010.5 1187.85  5044.9 1190.61  5081.7 1190.98
  5087.5 1188.74  5097.1 1188.58    5103 1190.55  5124.3 1191.66  5203.6 1191.86
  5329.2 1197.44    5335 1199.69  5350.5 1201.24    5379 1199.88  5387.2 1201.46
    5393 1199.08  5429.8 1199.48  5824.2 1210.22    5878 1209.96  5899.4 1209.91
#Mann= 7 ,-1 , 0
  4289.2     .12       0  4299.4     .05       0  4823.3     .12       0
  4903.3     .05       0    5006     .03       0  5010.5     .05       0
    5878     .12       0
Bank Sta=5006,5010.5
XS Rating Curve= 0 ,0
Exp/Cntr=0.3,0.1

Type RM Length L Ch R = 1 ,10500   ,500,500,500
BEGIN DESCRIPTION:
HICKORY01 21.0
END DESCRIPTION:
XS GIS Cut Line= 3
      2754955.69     10230053.11      2754449.62     10230580.61
      2753955.67     10231003.12
#Sta/Elev= 30
    4269 1208.93  4323.1  1207.2  4339.6 1206.44    4361 1206.83  4375.1 1205.18
  4434.8 1202.55  4502.5 1201.14  4537.7 1199.07  4643.7  1196.3  4771.1 1191.32
  4919.8 1190.31  4940.9 1188.65  4969.2 1188.72  4976.1 1187.66  4983.4 1187.94
    5000 1185.63  5009.3 1185.61  5009.7 1185.11    5014 1185.61  5025.9 1188.35
  5054.5 1190.09    5061 1189.06  5068.7 1190.25  5089.6 1190.21  5118.1 1192.29
  5132.4 1191.51  5153.3 1192.05  5175.2 1193.62  5493.6 1207.45    5650 1212.97
#Mann= 5 ,-1 , 0
    4269     .05       0  4323.1     .12       0  4434.8     .05       0
  5009.3     .03       0    5014     .05       0
Bank Sta=5009.3,5014
XS Rating Curve= 0 ,0
Exp/Cntr=0.3,0.1

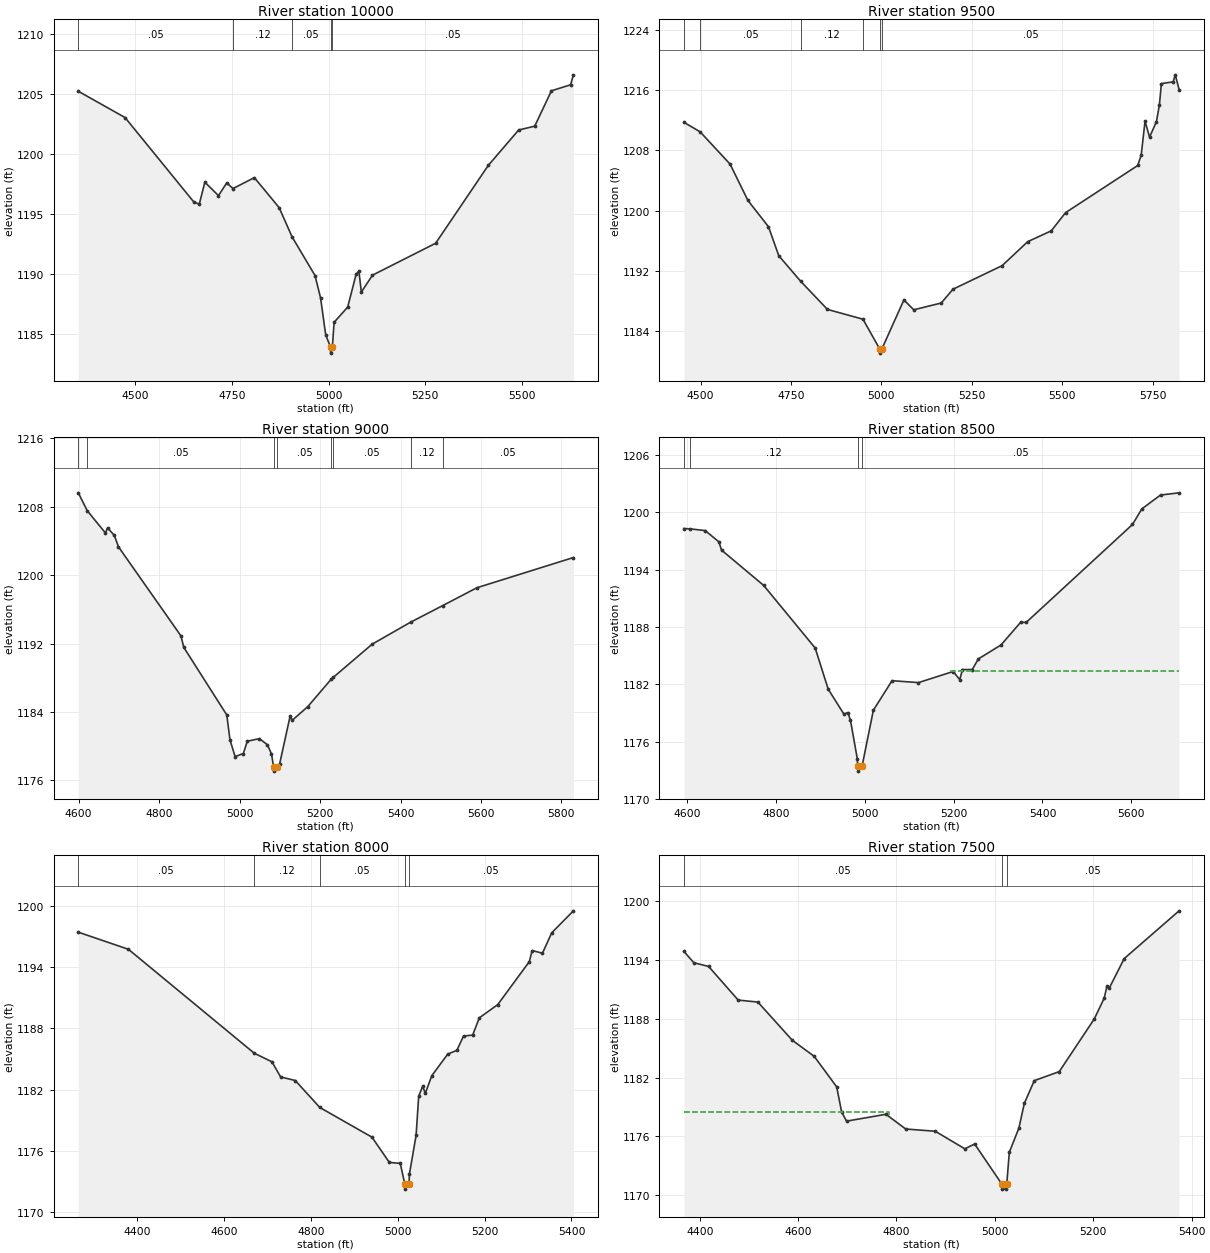
Type RM Length L Ch R = 1 ,10000   ,500,500,500
BEGIN DESCRIPTION:
HICKORY01 20.0
END DESCRIPTION:
XS GIS Cut Line= 3
      2754805.71     10229603.08      2754401.57     10230108.85
       2753905.7      10230503.1
#Sta/Elev= 30
  4352.6 1205.21  4473.5 1203.02  4651.2 1195.99  4665.6  1195.8    4680 1197.63
  4715.3 1196.51  4736.6 1197.57  4752.9  1197.1  4808.1 1198.01  4872.2 1195.51
  4905.7 1193.07    4965 1189.85  4979.4 1187.98  4992.6 1184.91  5005.1 1183.88
  5005.5 1183.38  5009.9 1183.88  5014.4 1185.95  5049.6 1187.22  5071.4 1189.96
  5078.5 1190.21  5084.9 1188.47  5113.7 1189.88  5277.1 1192.54  5413.3 1199.03
  5491.8 1201.98  5533.4  1202.3  5576.7 1205.25  5626.3 1205.75  5633.5 1206.58
#Mann= 5 ,-1 , 0
  4352.6     .05       0  4752.9     .12       0  4905.7     .05       0
  5005.1     .05       0  5009.9     .05       0
Bank Sta=5005.1,5009.9
XS Rating Curve= 0 ,0
Exp/Cntr=0.3,0.1

Type RM Length L Ch R = 1 ,9500    ,500,500,500
BEGIN DESCRIPTION:
HICKORY01 19.0
END DESCRIPTION:
XS GIS Cut Line= 3
      2754455.68     10229403.12      2754048.35     10229766.42
      2753805.68     10230553.14
#Sta/Elev= 30
  4454.2 1211.72  4498.8 1210.47  4581.7 1206.18    4631 1201.36  4687.9 1197.87
  4716.3 1194.03  4776.6 1190.65  4850.9  1186.9  4949.2  1185.6    4996  1181.6
  4996.3  1181.1  5000.9  1181.6  5062.3 1188.15  5089.7 1186.85  5165.5 1187.75
  5198.1 1189.58    5334 1192.71  5404.7 1195.89  5469.9 1197.33  5509.3 1199.74
    5709    1206  5718.6  1207.4  5729.1 1211.87  5741.6 1209.77  5760.5 1211.78
    5769 1214.08  5774.3 1216.86  5806.9  1217.1  5812.8 1218.03  5823.3 1216.08
#Mann= 6 ,-1 , 0
  4454.2     .12       0  4498.8     .05       0  4776.6     .12       0
  4949.2     .05       0    4996     .05       0  5000.9     .05       0
Bank Sta=4996,5000.9
XS Rating Curve= 0 ,0
Exp/Cntr=0.3,0.1

Type RM Length L Ch R = 1 ,9000    ,500,500,500
BEGIN DESCRIPTION:
HICKORY01 18.0
END DESCRIPTION:
XS GIS Cut Line= 3
      2754372.13     10229219.62      2753984.95     10229323.59
      2753155.67     10229353.11
#Sta/Elev= 30
  4599.1 1209.63  4621.3 1207.54  4666.6 1204.93  4671.7 1205.53  4688.6 1204.66
    4699 1203.31  4854.3 1192.89  4861.3 1191.55  4968.2 1183.64  4976.1 1180.74
  4988.9 1178.77  5009.3 1179.13  5019.3 1180.57  5049.3 1180.87  5069.3 1180.15
  5079.3 1179.08  5084.6 1177.57  5085.1 1177.07  5094.1 1177.57  5099.3 1177.86
  5125.7 1183.52  5130.7 1183.01  5169.4 1184.61  5228.4 1187.86  5233.1 1188.05
  5329.5 1191.92  5424.9 1194.49  5504.6 1196.43  5589.6 1198.52  5829.8 1202.06
#Mann= 8 ,-1 , 0
  4599.1     .12       0  4621.3     .05       0  5084.6     .05       0
  5094.1     .05       0  5228.4     .12       0  5233.1     .05       0
  5424.9     .12       0  5504.6     .05       0
Bank Sta=5084.6,5094.1
XS Rating Curve= 0 ,0
Exp/Cntr=0.3,0.1

Type RM Length L Ch R = 1 ,8500    ,500,500,500
BEGIN DESCRIPTION:
HICKORY01 17.0
END DESCRIPTION:
XS GIS Cut Line= 3
      2754092.66     10228683.99      2753745.58     10228896.37
      2753161.16     10229295.29
#Sta/Elev= 30
  4593.1 1198.28  4607.2 1198.25  4640.8 1198.07  4671.6  1196.9  4677.6 1196.03
  4772.4 1192.34  4888.4 1185.79  4917.8 1181.48    4953 1178.88  4961.9 1179.03
  4967.8 1178.24  4983.2 1174.22  4984.3 1173.41  4984.8 1172.91  4993.9 1173.41
  5019.4 1179.28  5061.4 1182.37    5121 1182.17  5198.9 1183.33  5213.9 1182.48
  5219.9 1183.53    5242 1183.54  5255.8 1184.65  5306.6  1186.1    5351 1188.48
  5363.5 1188.47  5602.7 1198.71  5623.7 1200.34  5665.8 1201.79  5707.6 1202.02
#Mann= 4 ,-1 , 0
  4593.1     .05       0  4607.2     .12       0  4984.3     .05       0
  4993.9     .05       0
#XS Ineff= 2 , 0
                         5193.08         1183.41
Permanent Ineff=
       F       F
Bank Sta=4984.3,4993.9
XS Rating Curve= 0 ,0
Exp/Cntr=0.3,0.1

Type RM Length L Ch R = 1 ,8000    ,500,500,500
BEGIN DESCRIPTION:
HICKORY01 16.0
END DESCRIPTION:
XS GIS Cut Line= 3
      2754081.04     10228643.25      2753346.58      10228620.9
      2753005.71     10228403.13
#Sta/Elev= 30
  4265.2 1197.43  4380.6 1195.75  4670.2 1185.57  4710.8 1184.73  4730.8 1183.25
  4764.4  1182.9  4820.9 1180.26  4940.9 1177.35  4980.9 1174.88  5006.1 1174.78
  5016.5 1172.76    5017 1172.26  5026.2 1172.76  5027.2 1173.74  5042.5 1177.52
  5048.5 1181.36  5057.7 1182.35  5063.6 1181.64  5078.8 1183.38  5115.2 1185.48
  5136.4 1185.86  5151.6 1187.25  5172.7 1187.35    5188 1189.04  5230.3 1190.33
    5303 1194.54  5309.6 1195.63  5333.3 1195.37  5354.6 1197.37  5404.5 1199.52
#Mann= 5 ,-1 , 0
  4265.2     .05       0  4670.2     .12       0  4820.9     .05       0
  5016.5     .03       0  5026.2     .05       0
Bank Sta=5016.5,5026.2
XS Rating Curve= 0 ,0
Exp/Cntr=0.3,0.1

Type RM Length L Ch R = 1 ,7500    ,500,500,500
BEGIN DESCRIPTION:
HICKORY01 15.0
END DESCRIPTION:
XS GIS Cut Line= 3
      2754155.66     10228203.11      2753524.68     10228167.21
      2753155.71     10228103.12
#Sta/Elev= 30
    4368 1194.86    4388 1193.71  4418.1 1193.33  4478.2  1189.9  4518.2  1189.7
  4588.3  1185.8  4632.7 1184.17  4678.5 1181.05  4688.5 1178.49  4698.5 1177.56
  4778.6 1178.26  4818.7 1176.76  4878.8 1176.53  4938.9 1174.74  4958.9 1175.23
  5014.4 1171.13  5014.9 1170.63  5023.6 1170.63  5024.1 1171.13  5029.4 1174.39
  5048.9 1176.86  5059.9 1179.38  5080.2 1181.69  5130.9 1182.61    5202 1187.97
  5222.3  1190.1  5227.9 1191.32    5233 1191.17  5262.9 1194.13  5374.5    1199
#Mann= 3 ,-1 , 0
    4368     .05       0  5014.4     .03       0  5024.1     .05       0
#XS Ineff= 2 , 0
         4785.79 1178.48
Permanent Ineff=
       F       F
Bank Sta=5014.4,5024.1
XS Rating Curve= 0 ,0
Exp/Cntr=0.3,0.1

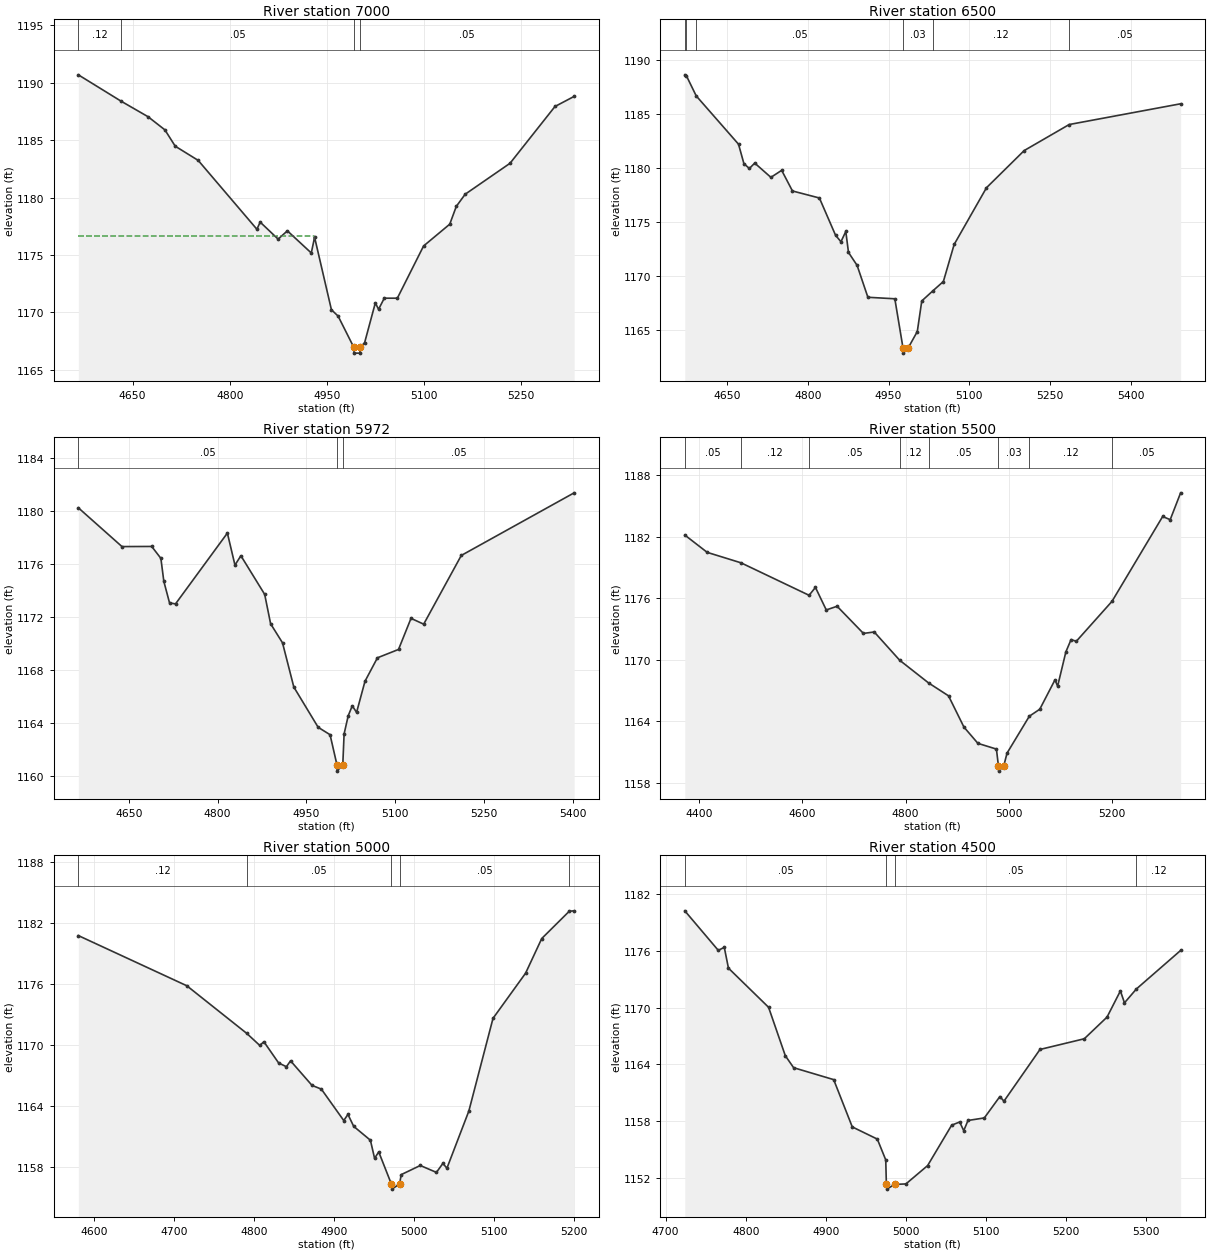
Type RM Length L Ch R = 1 ,7000    ,500,500,500
BEGIN DESCRIPTION:
HICKORY01 14.0
END DESCRIPTION:
XS GIS Cut Line= 3
      2754205.72     10227853.12      2753783.78     10227751.93
      2753455.69     10227703.11
#Sta/Elev= 30
  4566.1  1190.7  4632.2  1188.4  4673.7 1187.05  4699.8  1185.9  4715.7 1184.48
  4751.2 1183.24  4841.8 1177.24  4846.9 1177.86  4874.6 1176.38  4888.9  1177.1
  4925.8 1175.17  4930.9 1176.54  4956.9 1170.22  4967.2 1169.67  4991.5 1166.94
    4992 1166.44  5000.9 1166.44  5001.4 1166.94  5008.2 1167.36  5024.7 1170.82
  5029.7 1170.26  5038.5 1171.23  5058.7 1171.23  5099.2 1175.78  5139.6 1177.68
  5149.7 1179.23  5163.4 1180.29  5232.7 1182.99  5302.1 1187.94  5331.7 1188.82
#Mann= 4 ,-1 , 0
  4566.1     .12       0  4632.2     .05       0  4991.5     .03       0
  5001.4     .05       0
#XS Ineff= 2 , 0
         4930.05 1176.68
Permanent Ineff=
       F       F
Bank Sta=4991.5,5001.4
XS Rating Curve= 0 ,0
Exp/Cntr=0.3,0.1

Type RM Length L Ch R = 1 ,6500    ,528,528,528
BEGIN DESCRIPTION:
HICKORY01 13.0
END DESCRIPTION:
XS GIS Cut Line= 3
       2754395.4     10227280.89      2753967.42      10227291.1
       2753475.5     10227304.17
#Sta/Elev= 30
  4571.9 1188.64  4574.9 1188.55  4593.1 1186.69  4671.6 1182.22  4681.6 1180.42
  4691.7 1179.97  4701.7 1180.47  4731.7 1179.15  4751.7  1179.8  4771.7 1177.89
  4821.7 1177.24  4851.7 1173.79  4861.7 1173.19  4870.7 1174.14  4875.7  1172.2
  4891.7    1171  4911.7 1168.05  4961.7 1167.91  4976.8 1163.38  4977.3 1162.88
  4986.7 1163.38  5003.4 1164.88  5011.7 1167.71  5031.7 1168.62  5051.8 1169.51
  5071.8 1172.94  5131.8 1178.19  5201.8 1181.63  5285.3 1184.04  5492.1 1185.96
#Mann= 6 ,-1 , 0
  4571.9     .05       0  4574.9     .12       0  4593.1     .05       0
  4976.8     .03       0  5031.7     .12       0  5285.3     .05       0
Bank Sta=4976.8,4986.7
XS Rating Curve= 0 ,0
Exp/Cntr=0.3,0.1

Type RM Length L Ch R = 1 ,5972    ,472,472,472
BEGIN DESCRIPTION:
HICKORY01 12.0
END DESCRIPTION:
XS GIS Cut Line= 3
      2754209.13     10226855.87       2753775.5       10226894.
      2753482.47      10227169.2
#Sta/Elev= 30
  4564.7 1180.26  4638.4 1177.33  4688.6 1177.34  4704.1 1176.44  4709.1  1174.7
  4718.7 1173.08  4728.8    1173  4816.4 1178.35  4829.2 1175.93  4839.2 1176.64
  4879.4 1173.72  4889.4  1171.5  4909.5 1170.06  4928.6 1166.72  4969.7 1163.68
  4989.8 1163.12  5001.3 1160.87  5001.8 1160.37  5011.3 1160.87  5013.5 1163.18
  5020.5 1164.56  5027.3  1165.3  5034.6 1164.81  5048.8 1167.16  5069.8 1168.93
  5105.4 1169.56  5126.5 1171.91  5147.9 1171.47  5211.4 1176.66    5402 1181.39
#Mann= 3 ,-1 , 0
  4564.7     .05       0  5001.3     .03       0  5011.3     .05       0
Bank Sta=5001.3,5011.3
XS Rating Curve= 0 ,0
Exp/Cntr=0.3,0.1

Type RM Length L Ch R = 1 ,5500    ,500,500,500
BEGIN DESCRIPTION:
HICKORY01 11.0
END DESCRIPTION:
XS GIS Cut Line= 3
      2754205.65     10226803.09      2753685.07     10226451.83
      2753355.66     10226403.11
#Sta/Elev= 30
    4372 1182.16  4415.4 1180.47  4480.9 1179.45  4612.9 1176.28  4625.2 1177.05
  4646.2 1174.85  4667.2 1175.21  4718.2 1172.56  4739.2  1172.7  4788.5 1169.94
  4844.4 1167.73  4883.1 1166.47    4913 1163.42  4940.1 1161.83    4976 1161.27
  4979.9 1159.62  4980.4 1159.12  4990.1 1159.62  4996.6 1160.88  5039.8 1164.48
    5060 1165.16  5089.5 1168.03  5094.6 1167.41  5110.6 1170.76  5120.7 1171.96
  5130.8 1171.79    5200 1175.69  5298.2 1183.97  5312.8 1183.66    5333 1186.28
#Mann= 8 ,-1 , 0
    4372     .05       0  4480.9     .12       0  4612.9     .05       0
  4788.5     .12       0  4844.4     .05       0  4979.9     .03       0
  5039.8     .12       0    5200     .05       0
Bank Sta=4979.9,4990.1
XS Rating Curve= 0 ,0
Exp/Cntr=0.3,0.1

Type RM Length L Ch R = 1 ,5000    ,500,500,500
BEGIN DESCRIPTION:
HICKORY01 10.0
END DESCRIPTION:
XS GIS Cut Line= 3
      2754205.68      10226703.1      2754086.77     10226301.01
      2754055.69     10226103.14
#Sta/Elev= 30
  4580.7 1180.79  4716.3 1175.84  4791.1 1171.15  4807.4 1169.96  4812.6 1170.32
    4831 1168.23  4840.7 1167.86  4845.9 1168.44  4872.7 1166.02  4884.4 1165.65
  4912.4 1162.55  4917.6 1163.16  4924.8 1161.98  4945.7 1160.61  4950.9 1158.83
  4956.1 1159.46  4971.9 1156.29  4972.4 1155.79  4982.1 1156.29  4984.2 1157.22
    5008 1158.12  5028.2 1157.44  5036.3 1158.33  5041.3 1157.85  5068.7 1163.49
  5098.9 1172.63  5139.6 1177.08  5159.8  1180.5  5194.2 1183.19  5200.3 1183.23
#Mann= 5 ,-1 , 0
  4580.7     .12       0  4791.1     .05       0  4971.9     .03       0
  4982.1     .05       0  5194.2     .12       0
Bank Sta=4971.9,4982.1
XS Rating Curve= 0 ,0
Exp/Cntr=0.3,0.1

Type RM Length L Ch R = 1 ,4500    ,500,500,500
BEGIN DESCRIPTION:
HICKORY01 9.0
END DESCRIPTION:
XS GIS Cut Line= 3
      2754655.69     10226653.14       2754575.3       10226389.
      2754505.69     10226053.14
#Sta/Elev= 30
  4723.9 1180.24  4765.7 1176.06  4773.2 1176.38  4778.4 1174.18  4828.5 1170.04
  4849.4 1164.92  4859.8 1163.65  4909.8 1162.39    4933 1157.39  4964.3  1156.1
  4974.8  1153.9  4975.6 1151.31  4976.1 1150.81  4985.9 1151.31    5000 1151.36
  5027.1  1153.3  5057.1 1157.57  5067.1 1157.91  5072.2 1156.99  5077.5 1158.07
  5097.9 1158.34  5117.3  1160.6  5122.4 1160.11  5167.4 1165.58  5222.7 1166.71
  5251.1    1169  5267.8 1171.77  5272.9 1170.51  5287.8 1171.98    5343 1176.05
#Mann= 4 ,-1 , 0
  4723.9     .05       0  4975.6     .03       0  4985.9     .05       0
  5287.8     .12       0
Bank Sta=4975.6,4985.9
XS Rating Curve= 0 ,0
Exp/Cntr=0.3,0.1