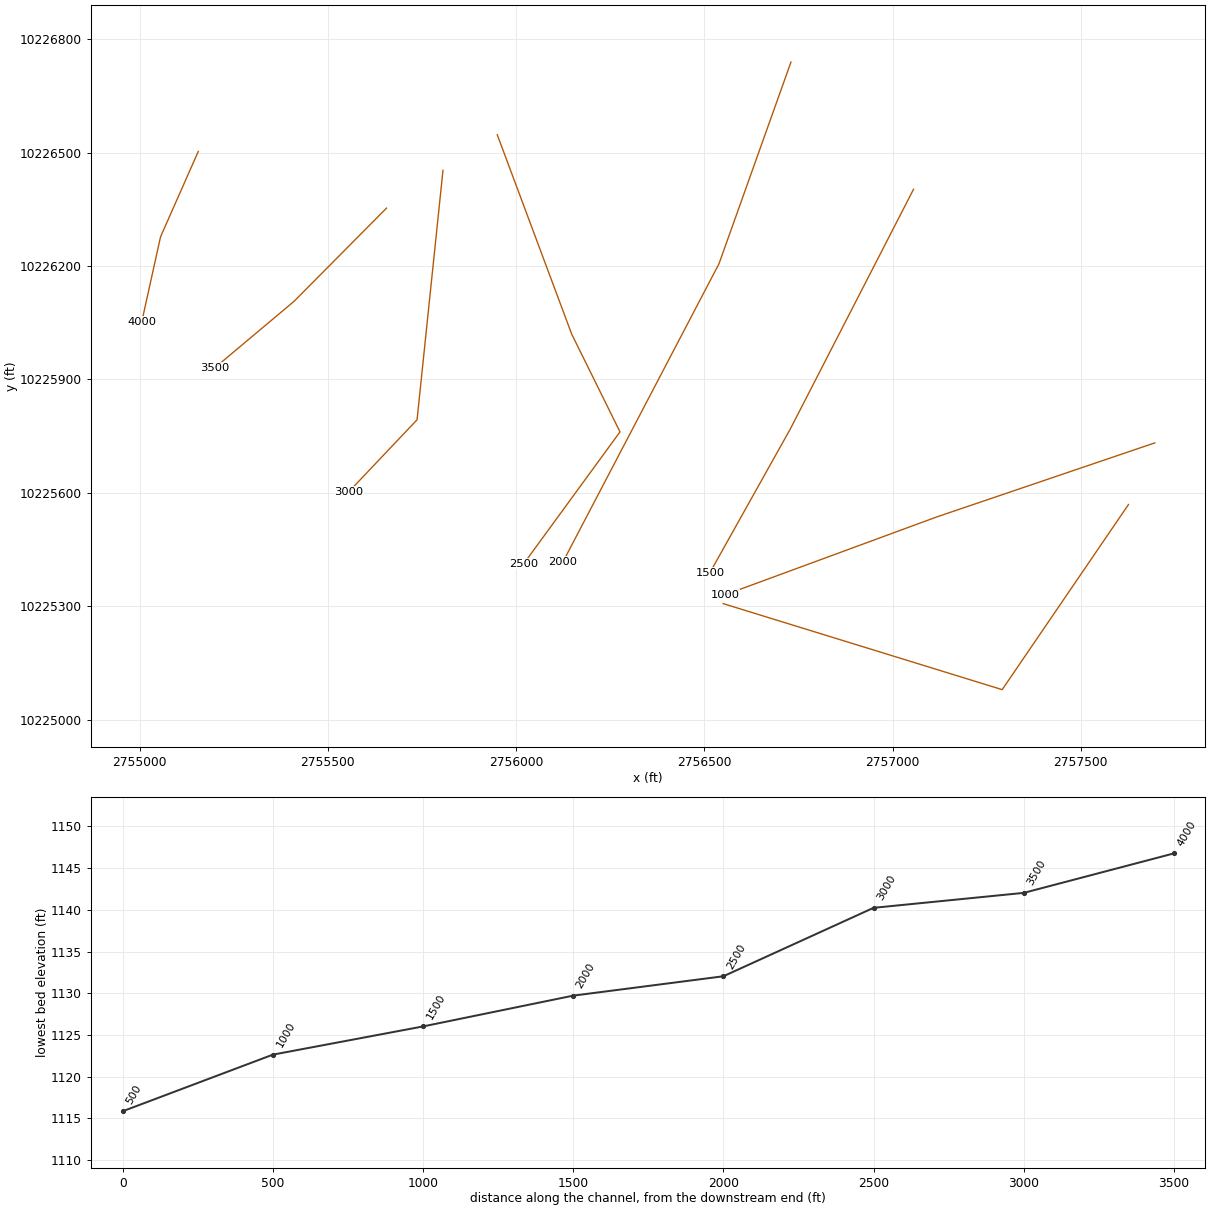
HEC-RAS study HICKORY01.prj: HICKORY01 Base Level Engineering

--- HICKORY01.g01 (geometry) --- (continued)

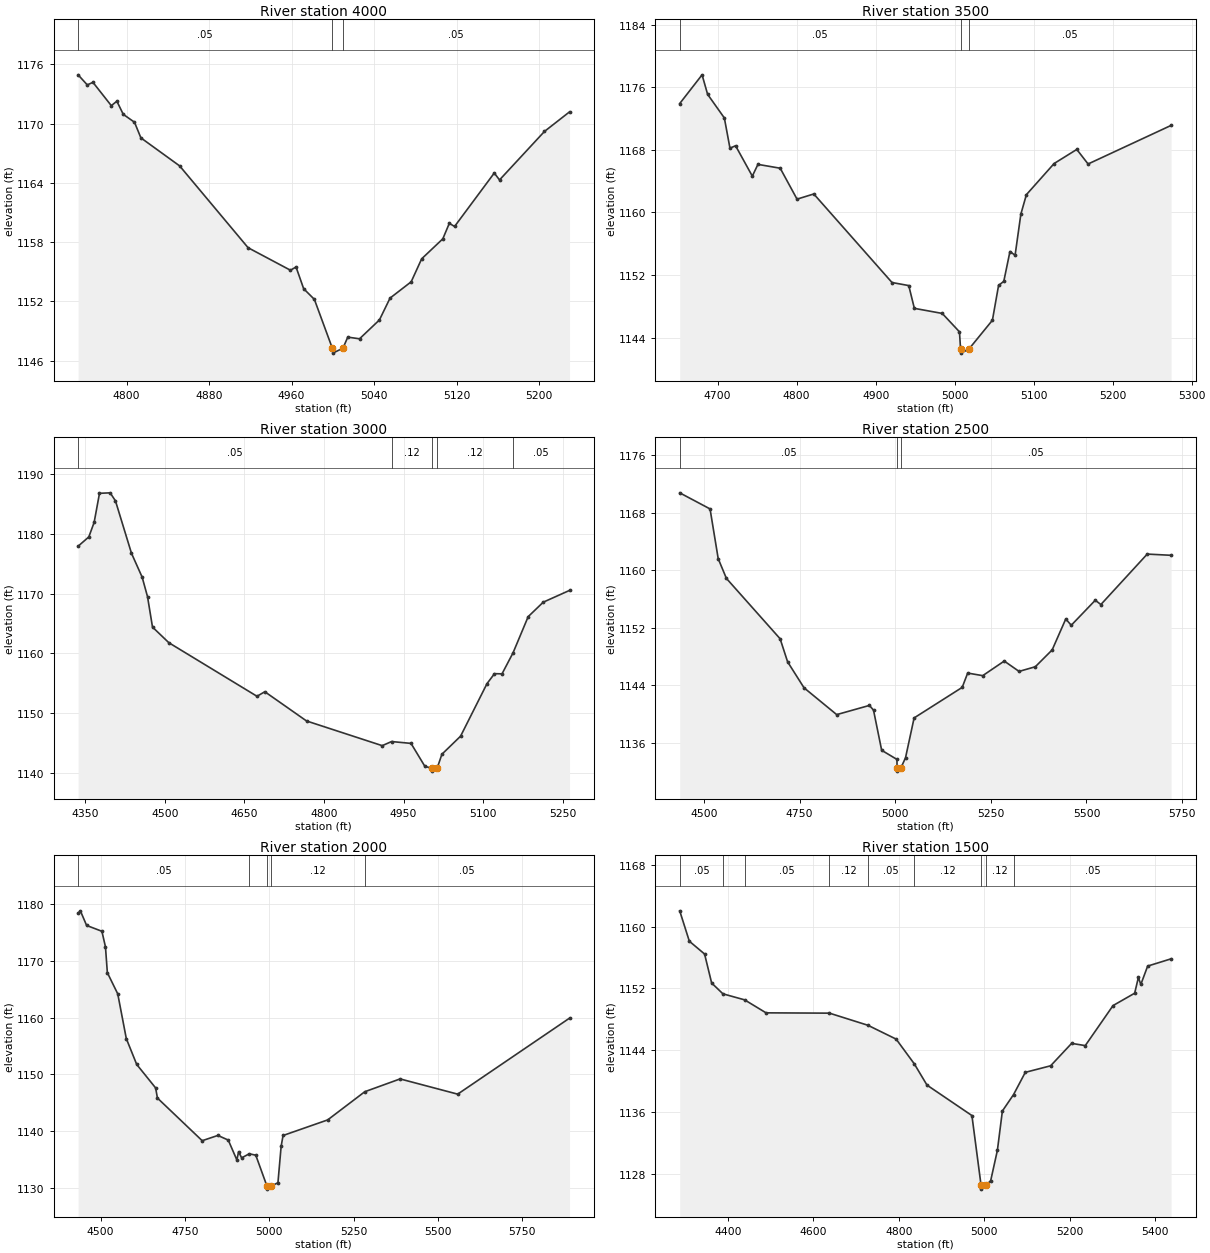
Type RM Length L Ch R = 1 ,4000    ,500,500,500
BEGIN DESCRIPTION:
HICKORY01 8.0
END DESCRIPTION:
XS GIS Cut Line= 3
      2755155.69     10226503.11      2755055.43     10226277.26
      2755005.69     10226053.12
#Sta/Elev= 30
  4752.9 1174.93  4761.8 1173.91  4767.3 1174.17  4785.1 1171.81  4790.5 1172.26
  4796.7 1170.93  4807.6 1170.13  4813.8 1168.55  4851.4 1165.71  4917.8 1157.43
  4958.9 1155.15  4964.3 1155.48  4971.7 1153.28  4982.1  1152.2  4999.5 1147.26
    5000 1146.76  5009.8 1147.26  5014.5 1148.38  5025.9 1148.21  5045.2 1150.12
  5055.5 1152.33    5076 1153.98  5086.2 1156.31  5106.7 1158.33    5113  1159.9
  5118.1 1159.58  5156.6 1164.99  5161.7 1164.29  5205.3  1169.2  5229.6 1171.18
#Mann= 3 ,-1 , 0
  4752.9     .05       0  4999.5     .03       0  5009.8     .05       0
Bank Sta=4999.5,5009.8
XS Rating Curve= 0 ,0
Exp/Cntr=0.3,0.1

Type RM Length L Ch R = 1 ,3500    ,500,500,500
BEGIN DESCRIPTION:
HICKORY01 7.0
END DESCRIPTION:
XS GIS Cut Line= 3
      2755655.67      10226353.1        2755410.     10226106.62
      2755199.74     10225930.93
#Sta/Elev= 30
    4652 1173.91  4680.3 1177.58  4687.3 1175.09  4708.5 1172.07  4715.6 1168.21
  4722.7 1168.52  4743.9 1164.64    4751 1166.14  4779.2 1165.65  4800.5  1161.7
  4821.7 1162.36  4920.7 1151.05  4941.9 1150.66    4949 1147.75  4984.3  1147.1
  5006.1 1144.75  5007.5 1142.53    5008 1142.03  5017.9 1142.53  5047.8 1146.23
  5055.6 1150.68  5062.2  1151.2    5070 1155.01  5076.5 1154.53  5083.8 1159.78
  5090.8 1162.27  5125.9 1166.25  5154.6 1168.05  5168.9 1166.19    5274 1171.12
#Mann= 3 ,-1 , 0
    4652     .05       0  5007.5     .05       0  5017.9     .05       0
Bank Sta=5007.5,5017.9
XS Rating Curve= 0 ,0
Exp/Cntr=0.3,0.1

Type RM Length L Ch R = 1 ,3000    ,500,500,500
BEGIN DESCRIPTION:
HICKORY01 6.0
END DESCRIPTION:
XS GIS Cut Line= 3
      2755805.69     10226453.16      2755736.83     10225793.34
      2755555.67      10225603.1
#Sta/Elev= 30
  4336.6 1177.95  4356.8 1179.51  4366.8 1181.94  4376.9 1186.82    4397  1186.9
    4407 1185.55  4437.2 1176.76  4457.3 1172.76  4467.4 1169.49  4476.8 1164.39
  4507.6 1161.77  4673.7 1152.79  4688.5 1153.55  4767.1 1148.65  4909.7 1144.51
  4927.4  1145.2    4964 1144.89  4990.2 1141.03  5002.9 1140.74  5003.4 1140.24
  5013.3 1140.74  5022.2 1143.07  5057.4  1146.1  5107.2 1154.91  5121.3 1156.58
  5135.5 1156.55  5156.3 1160.08  5184.8 1166.14  5213.1 1168.56  5262.7 1170.54
#Mann= 5 ,-1 , 0
  4336.6     .05       0  4927.4     .12       0  5002.9     .07       0
  5013.3     .12       0  5156.3     .05       0
Bank Sta=5002.9,5013.3
XS Rating Curve= 0 ,0
Exp/Cntr=0.3,0.1

Type RM Length L Ch R = 1 ,2500    ,500,500,500
BEGIN DESCRIPTION:
HICKORY01 5.0
END DESCRIPTION:
XS GIS Cut Line= 4
      2755949.87     10226547.34      2756147.54     10226020.08
      2756275.92     10225761.33      2756020.24     10225412.68
#Sta/Elev= 30
  4436.9 1170.75  4516.2 1168.51  4537.5 1161.59  4558.9 1158.85  4699.3 1150.45
  4718.9 1147.24  4761.8 1143.63  4847.2  1139.9  4932.7 1141.18  4943.4 1140.52
  4964.7 1134.94  5004.6 1133.67    5005 1132.54  5005.5 1132.04  5015.4 1132.54
    5027 1133.89  5049.5 1139.44  5175.2 1143.69  5189.5 1145.68  5228.8 1145.32
  5285.1 1147.35  5323.8 1145.91  5366.3 1146.56  5410.3  1148.9  5445.8  1153.2
  5460.2 1152.33    5523 1155.81  5537.6 1155.21  5658.8 1162.23  5721.2 1162.06
#Mann= 3 ,-1 , 0
  4436.9     .05       0    5005     .05       0  5015.4     .05       0
Bank Sta=5005,5015.4
XS Rating Curve= 0 ,0
Exp/Cntr=0.3,0.1

Type RM Length L Ch R = 1 ,2000    ,500,500,500
BEGIN DESCRIPTION:
HICKORY01 4.0
END DESCRIPTION:
XS GIS Cut Line= 3
      2756730.05     10226739.46      2756538.85     10226205.89
       2756124.6     10225417.94
#Sta/Elev= 30
  4433.2 1178.42  4439.9 1178.86  4458.4 1176.28  4503.7 1175.25  4514.3  1172.5
  4519.9 1167.94  4550.7  1164.2  4576.1  1156.3  4606.9 1151.74    4663 1147.59
  4668.4  1145.8  4801.1 1138.27  4847.6  1139.2  4878.4 1138.38  4903.8 1134.88
  4909.1 1136.33    4918 1135.24  4940.7 1135.96    4960 1135.71  4993.3 1130.22
  4993.8 1129.72  5004.3 1130.22  5025.7 1130.85  5035.2  1137.3  5040.9 1139.19
  5173.1 1141.94  5283.2 1146.92  5387.9 1149.18  5558.6 1146.49  5890.2 1159.91
#Mann= 5 ,-1 , 0
  4433.2     .05       0  4940.7     .12       0  4993.3     .07       0
  5004.3     .12       0  5283.2     .05       0
Bank Sta=4993.3,5004.3
XS Rating Curve= 0 ,0
Exp/Cntr=0.3,0.1

Type RM Length L Ch R = 1 ,1500    ,500,500,500
BEGIN DESCRIPTION:
HICKORY01 3.0
END DESCRIPTION:
XS GIS Cut Line= 3
      2757055.66     10226403.07      2756728.73     10225769.79
      2756514.62     10225388.71
#Sta/Elev= 30
  4287.3 1162.04  4309.8 1158.11  4345.5 1156.45    4362  1152.7  4388.4  1151.3
  4439.2 1150.52  4489.3 1148.84  4637.7  1148.8  4727.7 1147.23  4793.7 1145.44
  4836.3 1142.23  4865.9 1139.49    4971 1135.55  4992.4 1126.53  4992.9 1126.03
  5003.4 1126.53  5014.9 1127.12  5030.6 1131.05  5042.3 1136.14  5068.5 1138.27
  5095.9 1141.14  5155.2 1141.99  5204.3 1144.89  5236.2  1144.6  5301.2 1149.78
  5351.8 1151.38  5360.5 1153.42  5366.2 1152.51  5382.2 1154.89  5437.1 1155.83
#Mann= 9 ,-1 , 0
  4287.3     .05       0  4388.4     .12       0  4439.2     .05       0
  4637.7     .12       0  4727.7     .05       0  4836.3     .12       0
  4992.4     .07       0  5003.4     .12       0  5068.5     .05       0
Bank Sta=4992.4,5003.4
XS Rating Curve= 0 ,0
Exp/Cntr=0.3,0.1

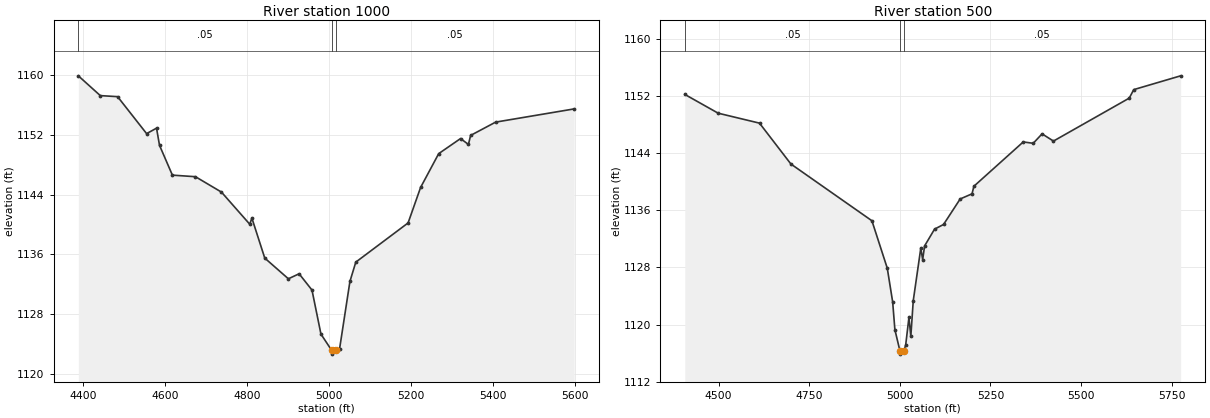
Type RM Length L Ch R = 1 ,1000    ,500,500,500
BEGIN DESCRIPTION:
HICKORY01 2.0
END DESCRIPTION:
XS GIS Cut Line= 3
      2757696.45      10225732.2      2757117.65     10225536.49
      2756555.39      10225330.5
#Sta/Elev= 30
    4389 1159.92  4442.6 1157.27  4484.8 1157.13  4555.6 1152.18  4579.8 1152.91
  4587.1 1150.61  4618.5 1146.62  4674.8 1146.41  4738.2 1144.35  4807.2 1140.05
  4812.5 1140.86  4843.9 1135.51  4901.5 1132.74  4927.7 1133.41  4959.1 1131.23
    4981 1125.33  5007.2 1123.15  5007.7 1122.65  5018.3 1123.15  5026.5 1123.38
  5051.7 1132.39    5066 1134.97  5193.6 1140.22  5224.1 1144.97  5268.3  1149.5
  5321.6 1151.52  5340.8 1150.73  5346.2 1151.94  5407.2 1153.72  5598.8 1155.49
#Mann= 3 ,-1 , 0
    4389     .05       0  5007.2     .05       0  5018.3     .05       0
Bank Sta=5007.2,5018.3
XS Rating Curve= 0 ,0
Exp/Cntr=0.3,0.1

Type RM Length L Ch R = 1 ,500     ,0,0,0
BEGIN DESCRIPTION:
HICKORY01 1.0
END DESCRIPTION:
XS GIS Cut Line= 3
      2757626.61     10225569.17      2757291.11      10225079.6
      2756550.12     10225307.03
#Sta/Elev= 30
  4406.5 1152.21  4498.7 1149.58  4612.7 1148.19  4699.4 1142.47    4923 1134.53
  4965.4 1127.89  4980.3 1123.16  4986.4 1119.29  5000.1 1116.37  5000.6 1115.87
  5011.2 1116.37  5016.1  1117.1  5025.2 1121.01  5030.4 1118.36  5037.1 1123.35
  5057.9 1130.69  5063.1  1129.1  5068.4 1131.01  5095.9 1133.36  5120.7 1134.01
  5166.6 1137.58  5199.3  1138.3  5204.5 1139.36  5340.7 1145.56  5368.2 1145.37
  5392.7 1146.69  5424.1 1145.68  5633.3 1151.69  5645.7 1152.88  5775.1 1154.81
#Mann= 3 ,-1 , 0
  4406.5     .05       0  5000.1     .05       0  5011.2     .05       0
Bank Sta=5000.1,5011.2
XS Rating Curve= 0 ,0
Exp/Cntr=0.3,0.1

Chan Stop Cuts=-1
Use User Specified Reach Order=0
Composite Channel Slope=5