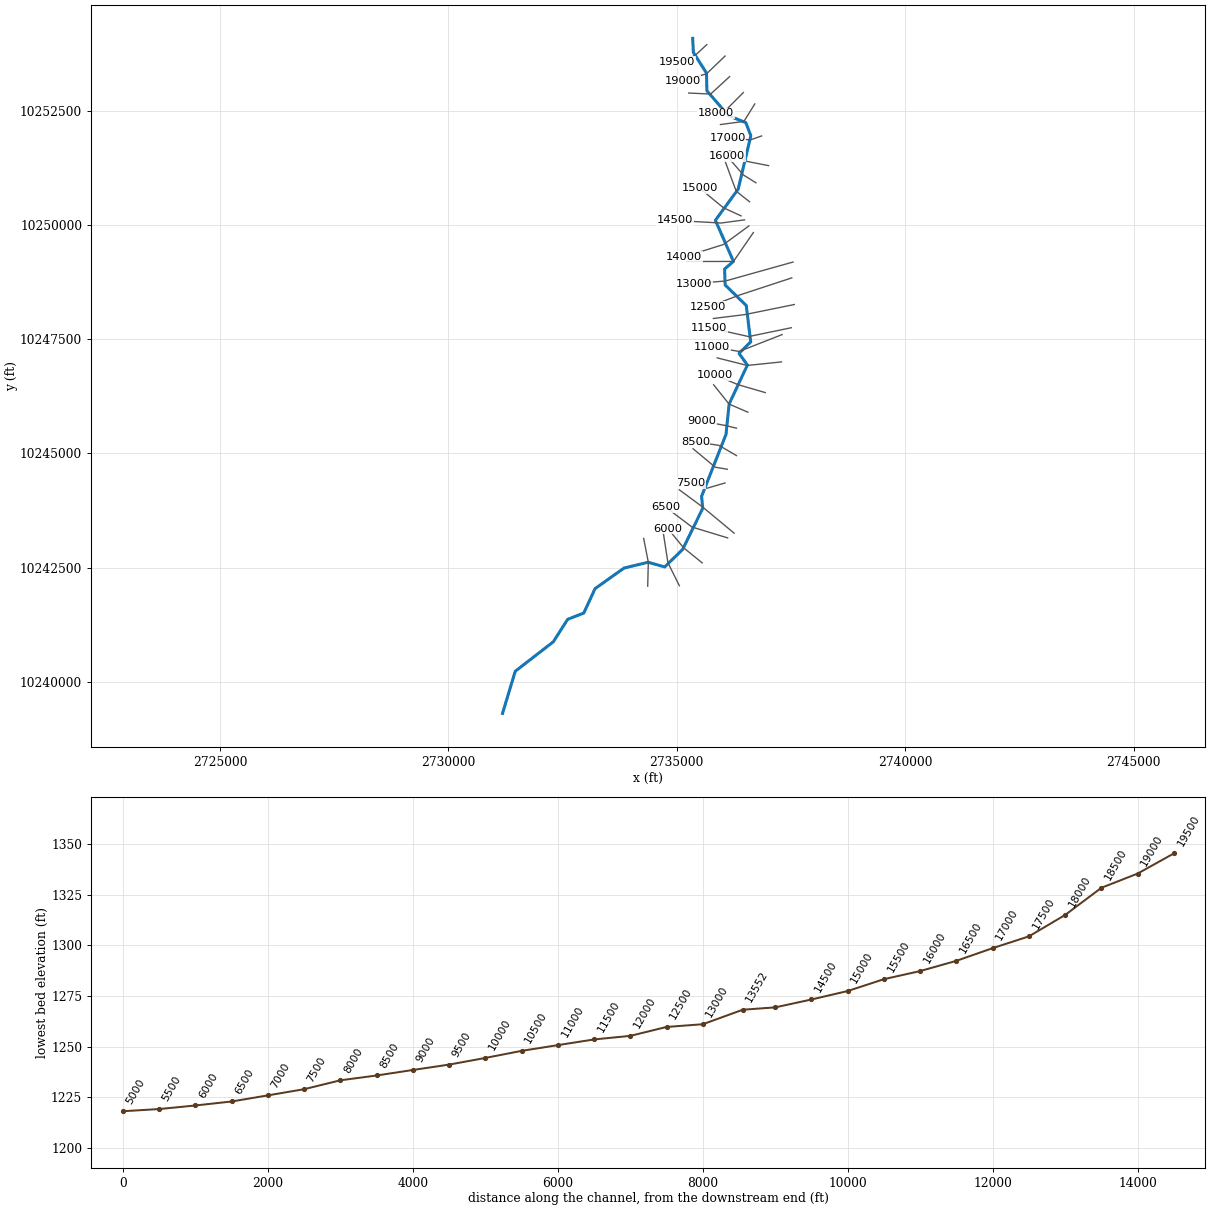
--- HICKORY05.prj (project) ---

Proj Title=HICKORY05 Base Level Engineering
Current Plan=p01
Default Exp/Contr=0.3,0.1
English Units
Geom File=g01
Flow File=f01
Plan File=p01
Y Axis Title=Elevation
X Axis Title(PF)=Main Channel Distance
X Axis Title(XS)=Station
BEGIN DESCRIPTION:
HICKORY05
END DESCRIPTION:
DSS Export Rating Curves= 0
DSS Export Rating Curve Sorted= 0
DSS Export Volume Flow Curves= 0
DXF OffsetX= 0
DXF OffsetY= 0
DXF ScaleX= 1
DXF ScaleY= 10

--- HICKORY05.p01 (plan) ---

Plan Title=Multiple Run
Short Identifier=Multiple
Geom File=g01
Flow File=f01
Subcritical Flow
K Sum by GR= 0
Std Step Tol= 0.01
Critical Tol= 0.01
Num of Std Step Trials= 20
Max Error Tol= 0.3
Flow Tol Ratio= 0.001
Split Flow NTrial= 30
Split Flow Tol= 0.02
Split Flow Ratio= 0.02
Log Output Level= 0
Friction Slope Method= 1
Unsteady Friction Slope Method= 2
Unsteady Bridges Friction Slope Method= 1
Parabolic Critical Depth
Global Vel Dist=  1 , 1 , 1
Global Log Level= 0
CheckData=True
Encroach Param= -1, 0, 0, 0
BEGIN DESCRIPTION:
Multiple Run
END DESCRIPTION:

--- HICKORY05.f01 (steady flow) ---

Flow Title=Multiple
Number of Profiles=7
Profile Names=10-year,25-year,50-year,1pct_min,100-year,1pct_plu,500-year
River Rch & RM= HICKORY05,Reach-1,19500
     450     732    1011     746    1356    2463    1877
River Rch & RM= HICKORY05,Reach-1,10500
     525     865    1159     828    1560    2936    2155
River Rch & RM= HICKORY05,Reach-1,8500
     729    1221    1745    1256    2378    4503    3276
River Rch & RM= HICKORY05,Reach-1,6000
    1316    2280    3436    2449    4773    9303    6513
Boundary for River Rch & Prof#=HICKORY05,Reach-1,1
Up Type=0
Dn Type=3
Dn Slope=0.005
Boundary for River Rch & Prof#=HICKORY05,Reach-1,2
Up Type=0
Dn Type=3
Dn Slope=0.005
Boundary for River Rch & Prof#=HICKORY05,Reach-1,3
Up Type=0
Dn Type=3
Dn Slope=0.005
Boundary for River Rch & Prof#=HICKORY05,Reach-1,4
Up Type=0
Dn Type=3
Dn Slope=0.005
Boundary for River Rch & Prof#=HICKORY05,Reach-1,5
Up Type=0
Dn Type=3
Dn Slope=0.005
Boundary for River Rch & Prof#=HICKORY05,Reach-1,6
Up Type=0
Dn Type=3
Dn Slope=0.005
Boundary for River Rch & Prof#=HICKORY05,Reach-1,7
Up Type=0
Dn Type=3
Dn Slope=0.005

--- HICKORY05.g01 (geometry) ---

Geom Title=Existing Conditions
Program Version=4.10

River Reach=HICKORY05       ,Reach-1
Reach XY= 30
      2735347.75       10254091.      2735361.75       10253784.
      2735649.75       10253330.       2735658.5       10252943.
       2736125.5       10252400.        2736511.       10252244.
      2736620.25       10251957.       2736342.5       10250787.
      2735844.25       10250106.      2736240.25       10249205.
      2736045.75       10249039.      2736057.75       10248689.
      2736519.75       10248240.      2736617.25       10247442.
        2736361.       10247192.      2736545.25       10246936.
      2736145.25       10246083.       2736076.5       10245417.
      2735542.25       10244061.      2735567.25       10243798.
       2735127.5       10242897.        2734736.       10242514.
       2734373.5       10242617.      2733845.25       10242489.
        2733211.       10242039.        2732964.       10241504.
        2732611.       10241367.      2732296.25       10240874.
        2731464.       10240229.      2731185.75       10239307.

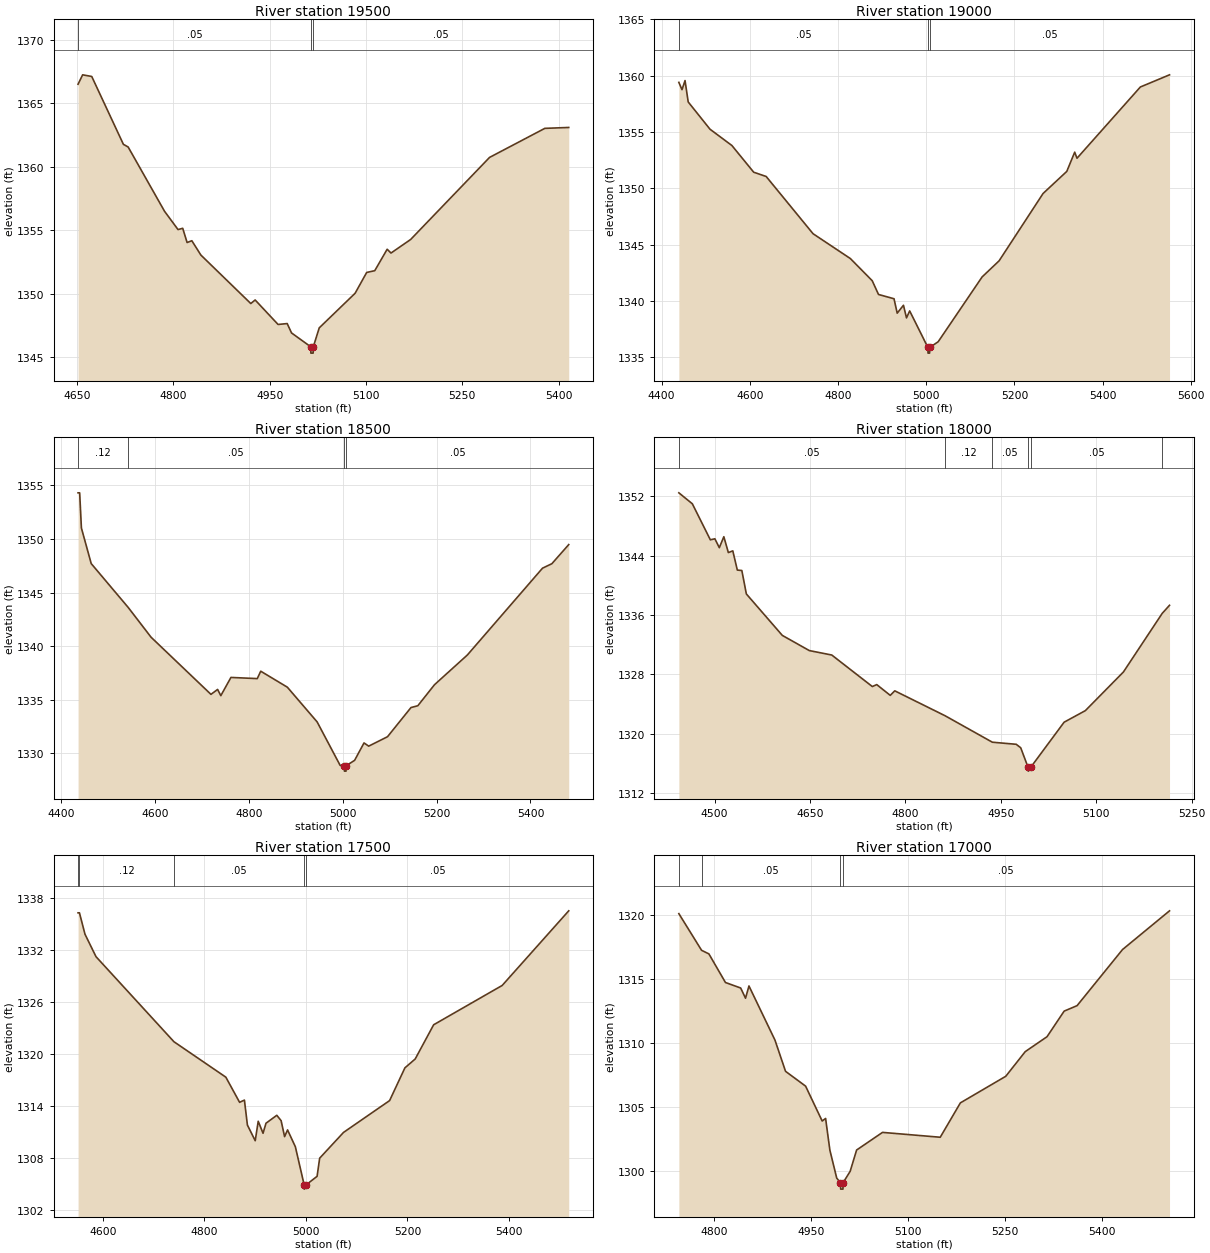
Type RM Length L Ch R = 1 ,19500   ,500,500,500
BEGIN DESCRIPTION:
HICKORY05 39.0
END DESCRIPTION:
XS GIS Cut Line= 3
      2735655.71     10253953.14      2735400.59     10253715.73
      2735009.82     10253573.94
#Sta/Elev= 30
  4651.5 1366.51  4658.6 1367.25  4672.8 1367.12  4722.1 1361.77  4729.5 1361.56
  4786.2 1356.49  4807.2 1355.05  4814.5 1355.15  4821.3 1354.03  4828.7 1354.17
  4842.8 1353.04  4920.5 1349.22  4927.3  1349.5    4963 1347.57  4977.2 1347.64
    4984  1346.9  5013.9 1345.81  5014.1 1345.31  5017.6 1345.31  5017.9 1345.81
  5027.1  1347.3    5083 1350.03    5101 1351.67  5113.6 1351.81  5132.9  1353.5
  5138.9  1353.2  5169.5 1354.27  5292.4 1360.74  5378.5 1363.03  5415.7  1363.1
#Mann= 3 ,-1 , 0
  4651.5     .05       0  5013.9     .03       0  5017.9     .05       0
Bank Sta=5013.9,5017.9
XS Rating Curve= 0 ,0
Exp/Cntr=0.3,0.1

Type RM Length L Ch R = 1 ,19000   ,500,500,500
BEGIN DESCRIPTION:
HICKORY05 38.0
END DESCRIPTION:
XS GIS Cut Line= 3
      2736055.68     10253703.11      2735651.35      10253314.5
      2735122.32     10253157.63
#Sta/Elev= 30
  4439.2 1359.41  4446.3 1358.76  4453.2 1359.57  4460.4 1357.67  4509.8 1355.25
  4559.5  1353.8  4608.9 1351.43  4637.2 1351.05  4743.4 1345.97  4828.1 1343.76
  4877.7 1341.79  4891.9 1340.57  4927.1 1340.19  4934.3 1338.91  4948.5 1339.61
  4955.4 1338.49  4962.6 1339.11  5003.9 1335.86  5004.2 1335.36  5007.7 1335.36
  5007.9 1335.86  5027.2 1336.37  5126.9 1342.13  5165.4 1343.56  5265.1 1349.54
  5318.8  1351.5  5336.8 1353.21    5342 1352.67  5485.7    1359  5551.8 1360.08
#Mann= 3 ,-1 , 0
  4439.2     .05       0  5003.9     .03       0  5007.9     .05       0
Bank Sta=5003.9,5007.9
XS Rating Curve= 0 ,0
Exp/Cntr=0.3,0.1

Type RM Length L Ch R = 1 ,18500   ,500,500,500
BEGIN DESCRIPTION:
HICKORY05 37.0
END DESCRIPTION:
XS GIS Cut Line= 3
      2736155.66     10253253.09      2735740.94      10252870.7
      2735259.86     10252893.06
#Sta/Elev= 30
  4435.9  1354.3  4439.3  1354.3    4443 1351.02  4463.9  1347.7  4542.9  1343.6
  4591.5 1340.83  4719.1  1335.5  4733.3 1335.96  4740.1 1335.38  4761.7 1337.08
  4817.8 1336.97  4825.2 1337.66  4881.9 1336.17  4945.4 1332.93  4994.5 1328.87
  5003.3 1328.84  5003.5 1328.34    5007 1328.34  5007.3 1328.84  5025.3 1329.35
  5045.3 1330.97  5055.3 1330.67  5095.4 1331.55  5145.4 1334.27    5160 1334.44
  5195.5  1336.4  5265.5 1339.17  5425.7 1347.27  5445.7 1347.69  5481.6 1349.47
#Mann= 4 ,-1 , 0
  4435.9     .12       0  4542.9     .05       0  5003.3     .05       0
  5007.3     .05       0
Bank Sta=5003.3,5007.3
XS Rating Curve= 0 ,0
Exp/Cntr=0.3,0.1

Type RM Length L Ch R = 1 ,18000   ,500,500,500
BEGIN DESCRIPTION:
HICKORY05 36.0
END DESCRIPTION:
XS GIS Cut Line= 3
      2736455.68     10252903.11       2736063.4     10252508.81
      2735855.64      10252453.1
#Sta/Elev= 30
  4443.8 1352.48    4465    1351  4493.3 1346.14  4500.4 1346.28  4507.4 1345.08
  4514.5 1346.56  4521.6 1344.42  4528.6 1344.65  4535.7 1342.06  4542.8    1342
  4549.9 1338.84  4606.4 1333.25  4648.9  1331.2  4684.2  1330.6  4747.9 1326.35
  4754.9 1326.61  4776.1 1325.16  4783.2 1325.77  4862.3 1322.41  4936.6 1318.84
  4974.1 1318.56  4981.2 1318.09  4992.8 1315.44  4993.1 1314.94  4996.8 1315.44
  5049.4 1321.54  5082.8  1323.1  5142.6 1328.31  5203.7 1336.23  5215.1 1337.31
#Mann= 6 ,-1 , 0
  4443.8     .05       0  4862.3     .12       0  4936.6     .05       0
  4992.8     .05       0  4996.8     .05       0  5203.7     .12       0
Bank Sta=4992.8,4996.8
XS Rating Curve= 0 ,0
Exp/Cntr=0.3,0.1

Type RM Length L Ch R = 1 ,17500   ,500,500,500
BEGIN DESCRIPTION:
HICKORY05 35.0
END DESCRIPTION:
XS GIS Cut Line= 3
      2736705.69     10252653.13        2736469.     10252271.46
      2735955.73     10252203.12
#Sta/Elev= 30
  4550.9 1336.33  4553.6 1336.33  4564.5 1333.86  4586.2 1331.26  4739.8 1321.42
  4842.1 1317.32  4869.2 1314.41  4878.7 1314.67  4884.6 1311.78    4900 1309.97
  4905.9 1312.22  4915.4 1310.83  4921.2 1311.99  4942.5 1312.91    4951 1312.29
  4957.9 1310.44  4963.7 1311.22  4979.1 1309.27  4996.4 1304.87  4996.6 1304.37
  5000.4 1304.87  5021.9 1305.85    5027 1307.95    5074 1310.93  5164.8 1314.61
    5195  1318.4  5215.2 1319.42  5251.6 1323.38  5386.7 1327.93  5517.8 1336.56
#Mann= 5 ,-1 , 0
  4550.9     .05       0  4553.6     .12       0  4739.8     .05       0
  4996.4     .05       0  5000.4     .05       0
Bank Sta=4996.4,5000.4
XS Rating Curve= 0 ,0
Exp/Cntr=0.3,0.1

Type RM Length L Ch R = 1 ,17000   ,500,500,500
BEGIN DESCRIPTION:
HICKORY05 34.0
END DESCRIPTION:
XS GIS Cut Line= 3
      2736855.72     10251953.12      2736616.02      10251868.5
       2736113.2     10251900.04
#Sta/Elev= 30
  4745.8 1320.12  4780.9 1317.25  4792.2 1316.97  4817.8 1314.73  4841.3  1314.3
  4848.8  1313.5  4854.1 1314.46  4894.3 1310.22  4910.6 1307.78  4941.6 1306.62
  4967.2 1303.89  4972.5 1304.09  4979.1 1301.61  4989.7 1299.42  4995.5 1299.06
  4995.8 1298.56  4999.3 1298.56  4999.5 1299.06  5010.4 1299.95  5020.4 1301.62
  5060.4    1303  5149.6 1302.62  5180.7 1305.31  5250.8 1307.39  5280.9 1309.32
  5314.6 1310.49    5341 1312.49    5361 1312.92  5431.2 1317.31  5503.8 1320.34
#Mann= 4 ,-1 , 0
  4745.8     .12       0  4780.9     .05       0  4995.5     .05       0
  4999.5     .05       0
Bank Sta=4995.5,4999.5
XS Rating Curve= 0 ,0
Exp/Cntr=0.3,0.1

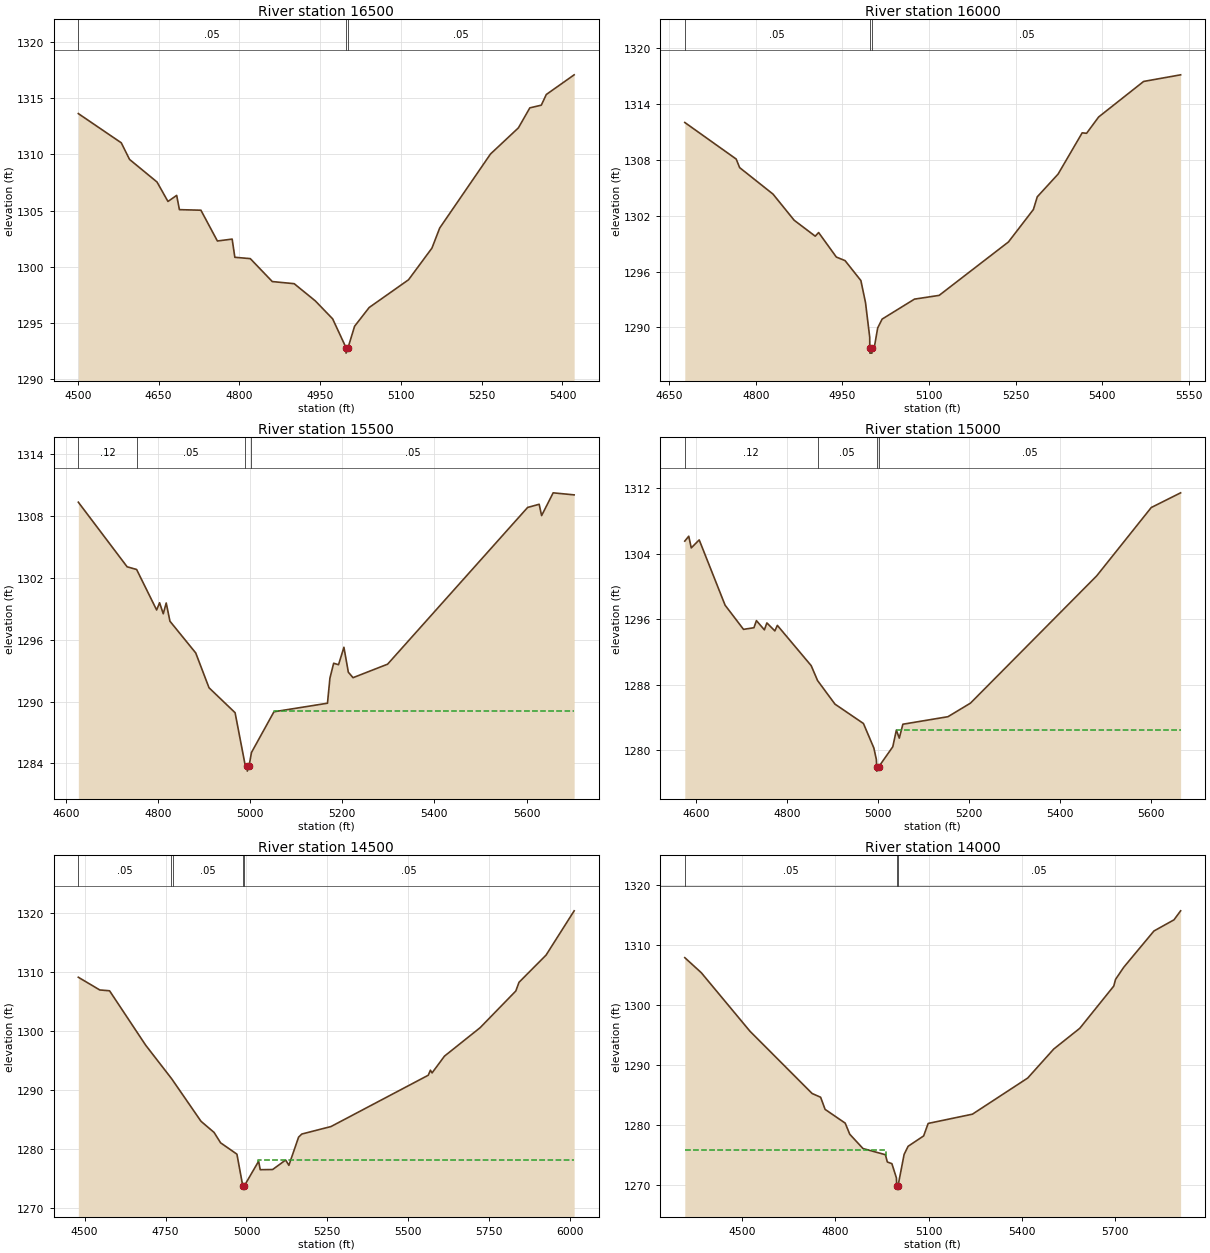
Type RM Length L Ch R = 1 ,16500   ,500,500,500
BEGIN DESCRIPTION:
HICKORY05 33.0
END DESCRIPTION:
XS GIS Cut Line= 3
      2737009.02     10251302.82      2736519.43     10251398.77
      2736161.82     10251622.26
#Sta/Elev= 30
  4501.1 1313.63  4580.8 1311.03  4596.2 1309.55  4647.2 1307.54  4667.5 1305.81
  4683.7 1306.35  4688.8 1305.08  4728.7 1305.03  4759.3 1302.29  4786.7 1302.46
  4791.7 1300.84  4820.4 1300.72  4861.2 1298.68  4901.9 1298.49  4941.1 1296.96
  4973.3 1295.36    4998 1292.81  4998.2 1292.31    5002 1292.81    5014  1294.7
  5041.1 1296.37  5114.2 1298.84  5157.7 1301.66    5172 1303.44  5266.3 1310.03
  5318.2 1312.36  5339.4 1314.14  5360.7 1314.38    5370 1315.33  5421.7 1317.08
#Mann= 3 ,-1 , 0
  4501.1     .05       0    4998     .05       0    5002     .05       0
Bank Sta=4998,5002
XS Rating Curve= 0 ,0
Exp/Cntr=0.3,0.1

Type RM Length L Ch R = 1 ,16000   ,500,500,500
BEGIN DESCRIPTION:
HICKORY05 32.0
END DESCRIPTION:
XS GIS Cut Line= 3
      2736731.24     10250927.83      2736457.24     10251098.68
      2736105.66     10251503.13
#Sta/Elev= 30
  4677.1 1311.98  4766.1 1308.06  4772.1 1307.14  4829.9  1304.3  4866.5  1301.5
    4903 1299.79  4908.9 1300.18  4939.6 1297.55  4954.7 1297.17  4982.1 1295.03
  4990.1 1292.67  4997.4 1288.95  4997.5 1287.75  4997.7 1287.25  5001.2 1287.25
  5001.5 1287.75    5005 1287.75  5011.2 1289.95  5018.9  1290.9  5074.9 1293.04
  5117.6 1293.44  5237.7 1299.17  5280.9 1302.65  5287.6 1304.01  5323.7 1306.45
  5365.4 1310.87    5373 1310.82  5393.9 1312.57  5471.8 1316.38  5535.9 1317.09
#Mann= 3 ,-1 , 0
  4677.1     .05       0  4997.5     .05       0  5001.5     .05       0
Bank Sta=4997.5,5001.5
XS Rating Curve= 0 ,0
Exp/Cntr=0.3,0.1

Type RM Length L Ch R = 1 ,15500   ,500,500,500
BEGIN DESCRIPTION:
HICKORY05 31.0
END DESCRIPTION:
XS GIS Cut Line= 3
      2736592.38     10250511.15       2736299.8     10250743.31
      2736055.69      10251403.1
#Sta/Elev= 30
  4626.5 1309.35  4732.5 1303.08  4753.1 1302.82  4796.6 1298.89    4803 1299.59
    4811 1298.52  4817.4 1299.57  4825.5  1297.8  4881.5 1294.72  4910.4 1291.34
    4967 1288.92  4988.9 1283.83  4993.3 1283.75  4993.5 1283.25  4997.3 1283.75
  5002.6 1285.06  5051.4 1289.01  5167.7 1289.84    5173 1292.28  5181.1 1293.72
  5191.7 1293.58  5203.4 1295.27    5213 1292.85  5223.2 1292.32  5298.3 1293.63
  5602.4 1308.84  5627.5 1309.15  5632.8 1308.05  5657.9 1310.26  5703.5 1310.06
#Mann= 4 ,-1 , 0
  4626.5     .12       0  4753.1     .05       0  4988.9     .05       0
  5002.6     .05       0
#XS Ineff= 2 , 0
                         5051.36         1289.08
Permanent Ineff=
       F       F
Bank Sta=4993.3,4997.3
XS Rating Curve= 0 ,0
Exp/Cntr=0.3,0.1

Type RM Length L Ch R = 1 ,15000   ,500,500,500
BEGIN DESCRIPTION:
HICKORY05 30.0
END DESCRIPTION:
XS GIS Cut Line= 3
      2736405.67     10250203.12      2736020.29     10250380.42
      2735505.65     10250803.14
#Sta/Elev= 30
  4575.8 1305.55  4584.5 1306.15    4590 1304.72  4607.5  1305.7  4664.4 1297.71
  4704.9 1294.75  4727.8 1294.95  4733.3 1295.82  4750.8 1294.69  4756.3 1295.54
  4773.8 1294.56  4779.3 1295.24  4853.7 1290.31  4867.7 1288.49    4906  1285.6
  4968.6 1283.23  4991.5 1280.23    4997 1278.83  4997.8  1277.9    4998  1277.4
  5001.8  1277.9  5033.1 1280.38    5041 1282.42  5047.4 1281.44  5055.3 1283.14
  5154.4 1284.06  5203.9 1285.72  5481.5  1301.3  5601.4 1309.66    5666 1311.46
#Mann= 4 ,-1 , 0
  4575.8     .12       0  4867.7     .05       0  4997.8     .05       0
  5001.8     .05       0
#XS Ineff= 2 , 0
                         5041.93         1282.43
Permanent Ineff=
       F       F
Bank Sta=4997.8,5001.8
XS Rating Curve= 0 ,0
Exp/Cntr=0.3,0.1

Type RM Length L Ch R = 1 ,14500   ,500,500,500
BEGIN DESCRIPTION:
HICKORY05 29.0
END DESCRIPTION:
XS GIS Cut Line= 3
      2736481.29     10250115.32      2735966.55     10250045.89
      2734955.67     10250103.11
#Sta/Elev= 30
  4480.6  1309.1  4546.8 1306.95  4577.1 1306.81  4688.6  1297.6  4768.4 1291.95
  4774.4 1291.48  4859.6 1284.71    4900 1282.82  4920.2 1281.06  4970.6 1279.14
  4988.8 1273.72    4989 1273.22  4992.8 1273.72  5037.6 1277.94  5042.6 1276.51
    5081 1276.54  5121.1 1278.15  5131.1 1277.25  5161.1 1282.02  5171.1 1282.55
  5261.3 1283.82  5561.8 1292.51  5568.4 1293.36  5573.5  1292.9  5611.8 1295.74
    5722 1300.56  5832.2 1306.77  5842.2 1308.25  5925.7 1312.85  6012.5 1320.35
#Mann= 5 ,-1 , 0
  4480.6     .05       0  4768.4     .12       0  4774.4     .05       0
  4988.8     .05       0  4992.8     .05       0
#XS Ineff= 2 , 0
                         5037.16         1278.07
Permanent Ineff=
       F       F
Bank Sta=4988.8,4992.8
XS Rating Curve= 0 ,0
Exp/Cntr=0.3,0.1

Type RM Length L Ch R = 1 ,14000   ,448,448,448
BEGIN DESCRIPTION:
HICKORY05 28.0
END DESCRIPTION:
XS GIS Cut Line= 3
      2736578.51     10249983.39        2736026.     10249577.46
      2735155.72     10249303.12
#Sta/Elev= 30
  4314.4 1307.87  4367.5 1305.37  4524.3 1295.63  4724.9 1285.25  4752.2 1284.63
  4766.6 1282.61  4831.4 1280.32  4846.1 1278.47  4888.7 1276.09    4961 1275.06
  4967.2 1273.85  4981.9 1273.57  4996.5 1271.19  4997.5 1269.83  4997.7 1269.33
  5001.5 1269.83  5021.3 1275.11  5034.1 1276.46  5084.2 1278.19  5098.8 1280.27
  5241.5 1281.81  5419.7 1287.83  5503.6 1292.66  5587.5 1296.11    5697 1303.14
  5702.8 1304.26  5729.3 1306.28  5826.4 1312.31  5891.1 1314.17  5912.5 1315.67
#Mann= 3 ,-1 , 0
  4314.4     .05       0  4997.5     .05       0  5001.5     .05       0
#XS Ineff= 2 , 0
         4961.93 1275.79
Permanent Ineff=
       F       F
Bank Sta=4997.5,5001.5
XS Rating Curve= 0 ,0
Exp/Cntr=0.3,0.1

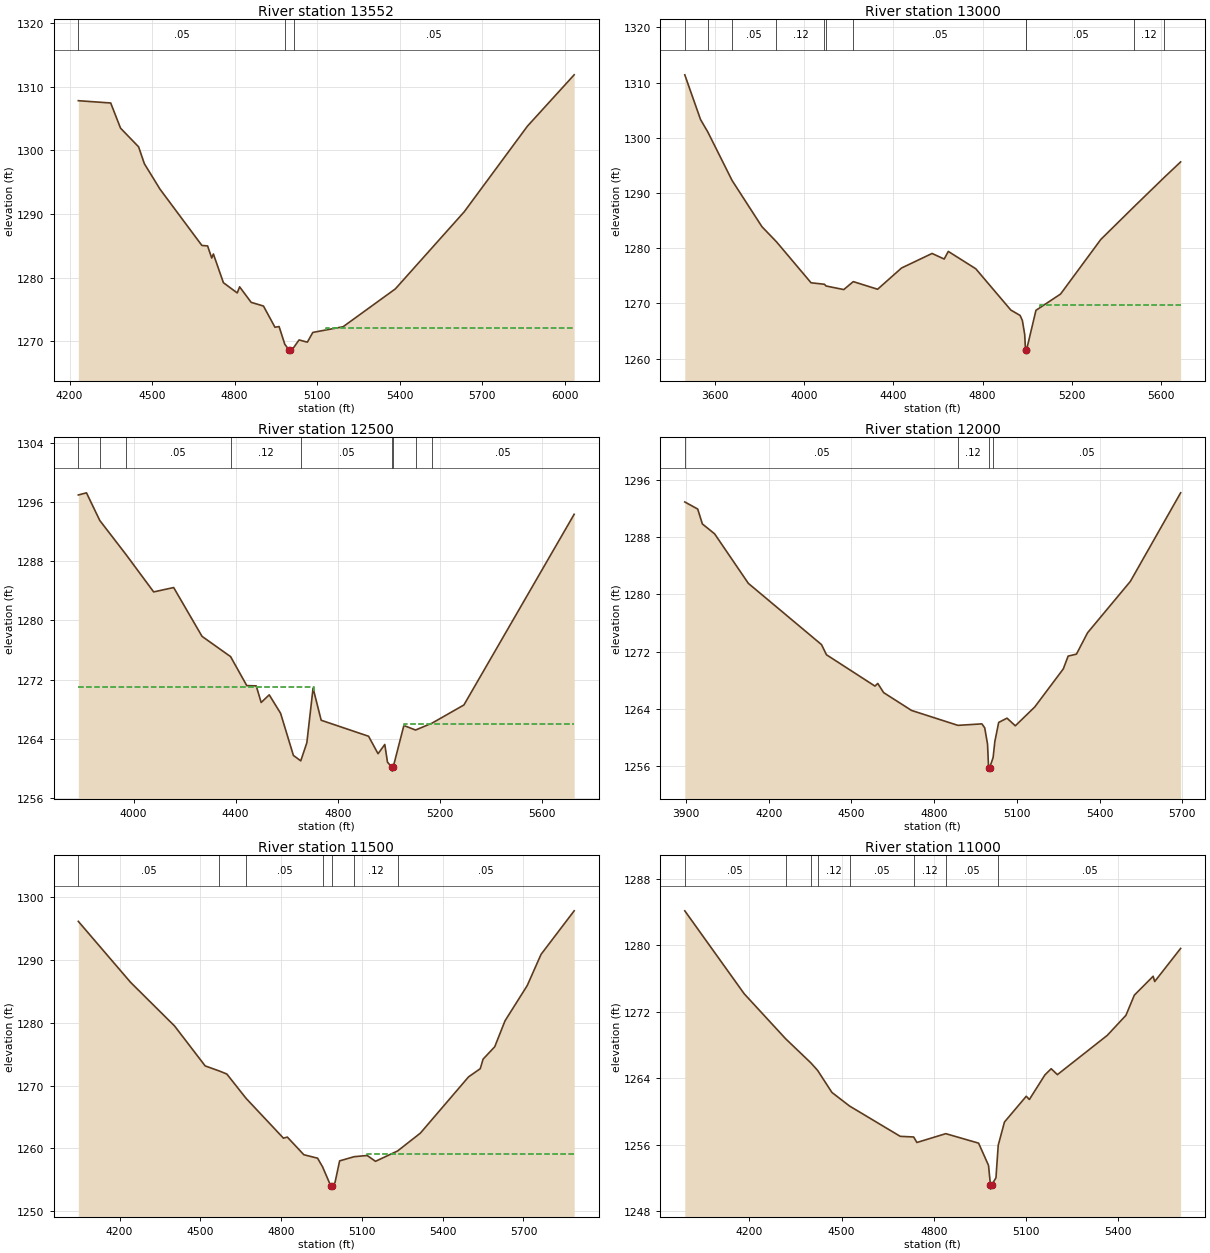
Type RM Length L Ch R = 1 ,13552   ,552,552,552
BEGIN DESCRIPTION:
HICKORY05 27.0
END DESCRIPTION:
XS GIS Cut Line= 3
      2736675.68     10249837.51      2736240.25       10249205.
      2735205.65     10249203.11
#Sta/Elev= 30
  4232.1 1307.78  4349.8 1307.42  4385.6 1303.47  4451.2 1300.54  4472.2 1297.89
    4529  1293.9  4681.2 1285.07  4702.1 1284.99    4717 1283.09  4723.1 1283.73
  4759.5 1279.22  4809.7 1277.62  4818.5 1278.57  4860.4 1276.14  4905.1 1275.56
    4947 1272.23  4961.9 1272.34  4982.8 1269.55    4998 1268.67  4998.3 1268.17
    5002 1268.67  5014.6 1269.03  5034.6 1270.24  5064.6 1269.89  5084.6 1271.42
  5194.6 1272.31  5384.6 1278.25  5634.6 1290.33  5864.6 1303.78  6034.6 1311.84
#Mann= 3 ,-1 , 0
  4232.1     .05       0  4982.8     .05       0  5014.6     .05       0
#XS Ineff= 2 , 0
                         5133.52         1272.14
Permanent Ineff=
       F       F
Bank Sta=4998,5002
XS Rating Curve= 0 ,0
Exp/Cntr=0.3,0.1

Type RM Length L Ch R = 1 ,13000   ,500,500,500
BEGIN DESCRIPTION:
HICKORY05 26.0
END DESCRIPTION:
XS GIS Cut Line= 3
      2737543.76     10249191.71      2736064.76     10248776.81
      2735378.94     10248719.64
#Sta/Elev= 30
  3463.9 1311.41  3534.6 1303.31  3567.4 1301.04  3676.2 1292.27  3810.1  1283.9
    3875 1281.18  4030.3 1273.75  4090.5 1273.48  4097.6 1273.17    4177 1272.52
  4219.8 1273.96  4328.9 1272.58  4436.4 1276.43  4573.2 1279.06  4627.6 1278.05
  4645.9 1279.43  4769.2 1276.29  4926.3 1268.82  4967.9 1267.84  4978.3 1266.93
  4988.7  1264.4  4992.5 1261.51  4992.8 1261.01  4996.5 1261.51  5039.2 1268.76
  5149.6 1271.71  5330.2  1281.6  5480.1 1287.56  5615.1 1292.85  5688.2 1295.64
#Mann= 11 ,-1 , 0
  3463.9     .05       0  3567.4     .12       0  3676.2     .05       0
    3875     .12       0  4090.5     .05       0  4097.6     .12       0
  4219.8     .05       0  4992.5     .05       0  4996.5     .05       0
  5480.1     .12       0  5615.1     .05       0
#XS Ineff= 2 , 0
                         5059.09         1269.64
Permanent Ineff=
       F       F
Bank Sta=4992.5,4996.5
XS Rating Curve= 0 ,0
Exp/Cntr=0.3,0.1

Type RM Length L Ch R = 1 ,12500   ,500,500,500
BEGIN DESCRIPTION:
HICKORY05 25.0
END DESCRIPTION:
XS GIS Cut Line= 3
      2737516.01      10248844.5      2736360.68     10248464.89
      2735682.66      10248205.6
#Sta/Elev= 30
  3783.9 1296.95  3815.8 1297.24  3867.9 1293.51  3970.4 1288.92    4079 1283.86
  4157.3 1284.45  4268.4 1277.86  4380.3 1275.12  4443.6 1271.21  4480.7 1271.17
    4500 1268.93  4531.6 1269.96  4576.1 1267.47  4626.3 1261.78  4655.1 1261.05
  4678.9 1263.49  4703.3 1270.87  4735.1 1266.53  4920.7 1264.37  4957.8 1262.01
  4984.2 1263.26  4994.8 1260.87  5012.8 1260.16  5013.1 1259.66  5016.8 1260.16
  5058.9 1265.82  5104.8 1265.21  5169.2 1266.14    5294 1268.59  5725.9 1294.34
#Mann= 9 ,-1 , 0
  3783.9     .05       0  3867.9     .12       0  3970.4     .05       0
  4380.3     .12       0  4655.1     .05       0  5012.8     .05       0
  5016.8     .05       0  5104.8     .12       0  5169.2     .05       0
#XS Ineff= 2 , 0
         4708.81 1271.01 5058.24         1266.07
Permanent Ineff=
       F       F
Bank Sta=5012.8,5016.8
XS Rating Curve= 0 ,0
Exp/Cntr=0.3,0.1

Type RM Length L Ch R = 1 ,12000   ,500,500,500
BEGIN DESCRIPTION:
HICKORY05 24.0
END DESCRIPTION:
XS GIS Cut Line= 3
      2737571.56     10248261.16      2736489.18     10248040.73
      2735800.72      10247955.6
#Sta/Elev= 30
  3895.4 1292.96  3942.2 1291.97  3959.2 1289.88  4003.5  1288.5  4125.9 1281.56
  4391.3 1272.98  4409.2 1271.56  4585.2 1267.17  4595.4 1267.54  4616.5 1266.26
  4717.8 1263.76  4886.1 1261.67    4973 1261.88  4983.2 1261.32  4993.4 1259.05
  4997.2 1255.76  4997.5 1255.26  5001.2 1255.76  5013.6 1257.16    5020 1259.43
  5033.8 1262.08    5064 1262.68  5094.2 1261.61  5164.7 1264.25  5268.2 1269.58
  5285.7 1271.37  5315.9 1271.65  5356.2 1274.64  5511.3 1281.83  5693.7 1294.24
#Mann= 4 ,-1 , 0
  3895.4     .05       0  4886.1     .12       0  4997.2     .05       0
  5013.6     .05       0
Bank Sta=4997.2,5001.2
XS Rating Curve= 0 ,0
Exp/Cntr=0.3,0.1

Type RM Length L Ch R = 1 ,11500   ,500,500,500
BEGIN DESCRIPTION:
HICKORY05 23.0
END DESCRIPTION:
XS GIS Cut Line= 3
      2737505.68     10247753.11      2736572.48     10247559.36
      2735705.67     10247753.12
#Sta/Elev= 30
  4046.9 1296.16  4240.9 1286.45  4404.4 1279.49    4518 1273.13    4570 1272.33
  4598.4 1271.84  4669.9 1267.96  4808.6 1261.62  4823.1 1261.79  4884.4 1258.98
  4935.4 1258.43  4953.9 1257.05  4984.5    1254  4984.8  1253.5  4988.5    1254
    5000 1254.53  5017.2    1258  5071.4 1258.67  5119.7 1258.86  5150.4 1257.93
  5232.5 1259.58  5317.3 1262.43  5496.1 1271.39  5539.5 1272.69    5550 1274.21
  5593.2 1276.18  5631.5 1280.32    5714 1285.94  5765.2  1290.9  5888.2 1297.84
#Mann= 7 ,-1 , 0
  4046.9     .05       0    4570     .12       0  4669.9     .05       0
  4953.9     .05       0  4988.5     .05       0  5071.4     .12       0
  5232.5     .05       0
#XS Ineff= 2 , 0
                         5119.32         1259.05
Permanent Ineff=
       F       F
Bank Sta=4984.5,4988.5
XS Rating Curve= 0 ,0
Exp/Cntr=0.3,0.1

Type RM Length L Ch R = 1 ,11000   ,500,500,500
BEGIN DESCRIPTION:
HICKORY05 22.0
END DESCRIPTION:
XS GIS Cut Line= 3
      2737305.71     10247603.12      2736365.26     10247234.26
      2735770.06     10247332.23
#Sta/Elev= 30
  3989.8 1284.16  4183.2 1274.18  4317.5 1268.79  4400.4 1265.86  4421.8 1264.98
  4468.5 1262.32  4526.1 1260.68  4690.8 1257.04  4734.7 1256.96    4745  1256.3
    4839 1257.36  4945.8 1256.22  4978.1 1253.55  4984.4 1251.19  4984.7 1250.69
  4988.4 1251.19  5002.3 1252.05  5009.7 1255.97    5030 1258.76  5100.9 1261.86
    5111 1261.47  5161.7 1264.43    5182 1265.17  5202.3 1264.46  5364.4 1269.18
  5425.2 1271.59  5452.6 1274.02  5513.8 1276.29  5518.9 1275.66  5603.2 1279.64
#Mann= 8 ,-1 , 0
  3989.8     .05       0  4317.5     .12       0  4400.4     .05       0
  4421.8     .12       0  4526.1     .05       0  4734.7     .12       0
    4839     .05       0  5009.7     .05       0
Bank Sta=4984.4,4988.4
XS Rating Curve= 0 ,0
Exp/Cntr=0.3,0.1

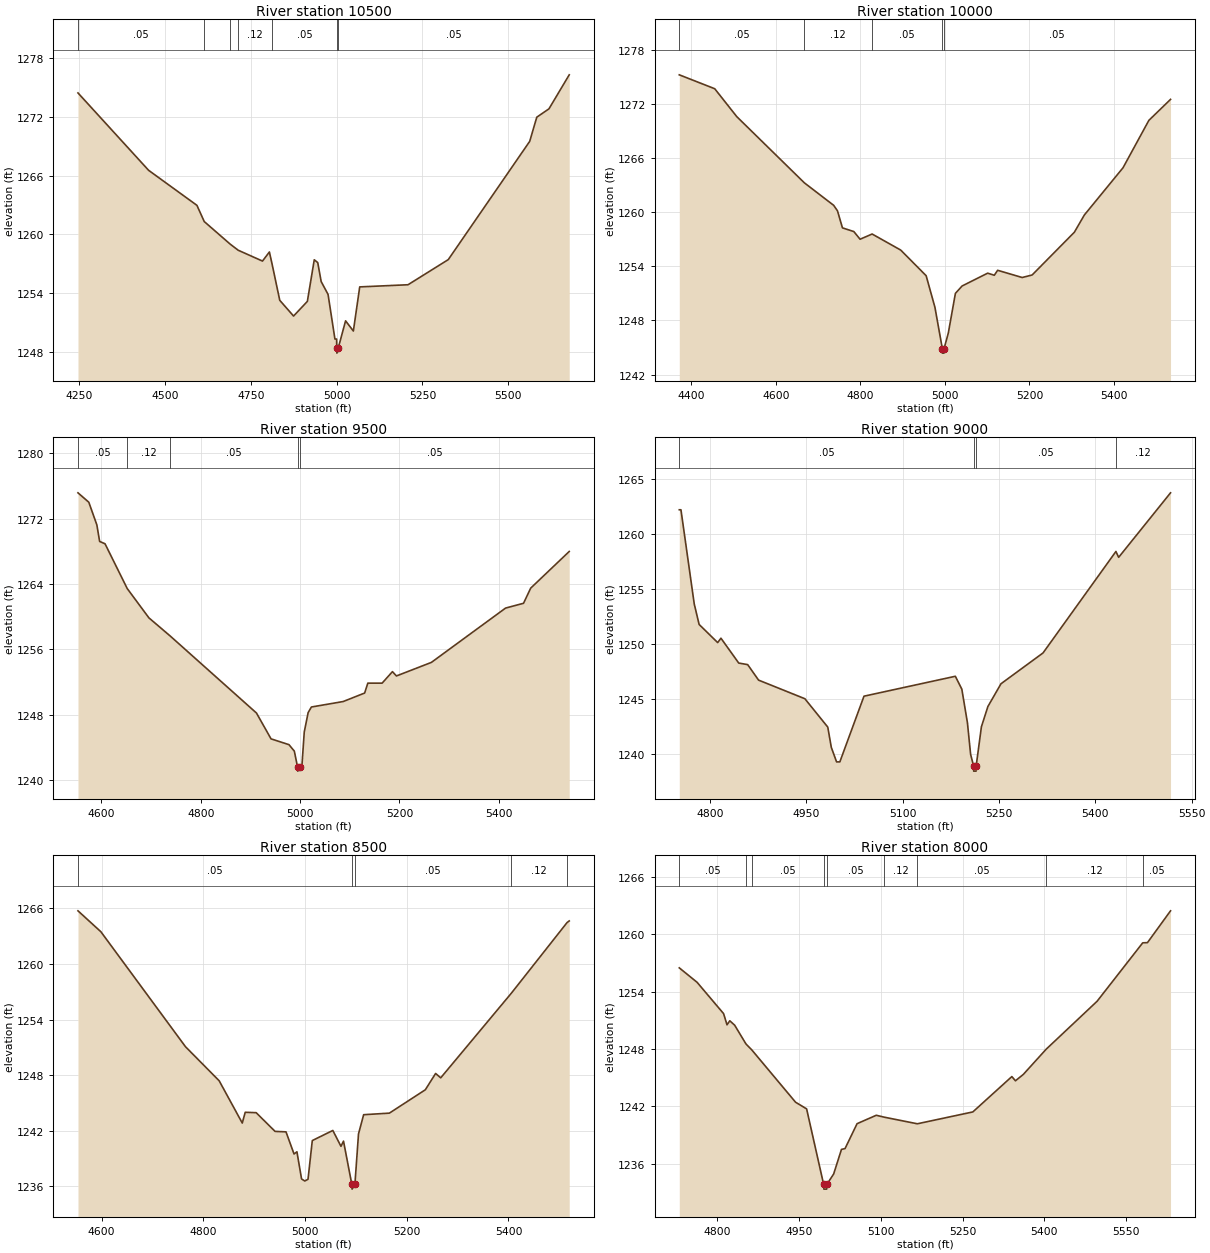
Type RM Length L Ch R = 1 ,10500   ,500,500,500
BEGIN DESCRIPTION:
HICKORY05 21.0
END DESCRIPTION:
XS GIS Cut Line= 3
      2737290.29     10247004.21      2736540.96     10246926.92
      2735884.07     10247092.74
#Sta/Elev= 30
  4246.7 1274.46  4452.4 1266.55  4593.1 1262.97  4614.5 1261.31  4689.8 1259.01
  4713.3 1258.38  4784.1 1257.27  4804.2  1258.2  4812.2 1256.94  4834.4 1253.26
  4874.6 1251.65  4914.8 1253.15  4934.9  1257.4    4945 1257.12    4955 1255.18
  4975.1 1253.86  4995.1  1249.3    5000  1249.3  5000.5 1248.36  5000.8 1247.86
  5004.6 1248.36  5026.1 1251.16  5048.8 1250.12  5067.3 1254.63  5207.9 1254.85
  5325.2 1257.42  5562.4 1269.51    5583 1271.98  5618.4 1272.83  5677.5 1276.31
#Mann= 7 ,-1 , 0
  4246.7     .05       0  4614.5     .12       0  4689.8     .05       0
  4713.3     .12       0  4812.2     .05       0  5000.5     .05       0
  5004.6     .05       0
Bank Sta=5000.5,5004.6
XS Rating Curve= 0 ,0
Exp/Cntr=0.3,0.1

Type RM Length L Ch R = 1 ,10000   ,500,500,500
BEGIN DESCRIPTION:
HICKORY05 20.0
END DESCRIPTION:
XS GIS Cut Line= 3
      2736936.15     10246332.33      2736333.16     10246508.14
      2735842.34     10246717.76
#Sta/Elev= 30
  4371.9 1275.21  4455.7 1273.67  4507.8 1270.58  4667.7 1263.24    4737 1260.75
    4746 1260.14  4757.8 1258.25  4784.7 1257.84  4799.5 1256.99  4827.9 1257.57
  4895.6 1255.79  4955.7 1252.95  4976.5 1249.45    4994 1244.87  4994.2 1244.37
  4997.8 1244.37  4998.1 1244.87  5008.1 1246.59  5024.9 1250.99  5040.7 1251.81
  5101.2 1253.23  5116.9    1253  5124.8 1253.55  5182.8 1252.75  5206.4 1253.03
  5306.3 1257.77  5329.9 1259.68  5421.3 1264.91  5482.4 1270.16  5533.7 1272.49
#Mann= 5 ,-1 , 0
  4371.9     .05       0  4667.7     .12       0  4827.9     .05       0
    4994     .05       0  4998.1     .05       0
Bank Sta=4994,4998.1
XS Rating Curve= 0 ,0
Exp/Cntr=0.3,0.1

Type RM Length L Ch R = 1 ,9500    ,500,500,500
BEGIN DESCRIPTION:
HICKORY05 19.0
END DESCRIPTION:
XS GIS Cut Line= 3
      2736555.71      10245903.1      2736145.08     10246080.48
      2735805.71     10246503.08
#Sta/Elev= 30
  4552.7 1275.15  4574.5    1274  4590.7 1271.23  4596.3  1269.2  4607.2 1268.91
  4651.9 1263.43  4695.6 1259.84  4738.1 1257.64  4912.2 1248.19  4941.5 1245.03
  4977.6 1244.32  4988.4 1243.53  4994.9 1241.58  4995.2 1241.08  4999.1 1241.58
  5003.5 1241.58  5008.4 1245.87  5016.2 1248.24  5022.8 1248.93  5086.8  1249.6
    5130 1250.64  5136.4 1251.85  5165.2 1251.85    5186 1253.26    5194 1252.73
  5264.4 1254.39  5413.8 1261.04    5450 1261.63  5464.4 1263.48    5542 1267.97
#Mann= 5 ,-1 , 0
  4552.7     .05       0  4651.9     .12       0  4738.1     .05       0
  4994.9     .05       0  4999.1     .05       0
Bank Sta=4994.9,4999.1
XS Rating Curve= 0 ,0
Exp/Cntr=0.3,0.1

Type RM Length L Ch R = 1 ,9000    ,500,500,500
BEGIN DESCRIPTION:
HICKORY05 18.0
END DESCRIPTION:
XS GIS Cut Line= 3
      2736305.67     10245553.12      2736064.71     10245612.21
      2735555.66     10245703.12
#Sta/Elev= 30
  4751.9 1262.18  4754.5 1262.18  4775.2 1253.62  4782.8 1251.76  4811.7 1250.11
  4816.8 1250.51  4844.5 1248.25  4858.4 1248.11  4875.4  1246.7  4947.5 1245.01
  4983.2 1242.43  4988.7 1240.59  4996.9 1239.27    5002 1239.27  5039.6 1245.24
  5181.9 1247.05    5192 1245.88  5200.7 1242.84  5205.7 1239.95  5210.2 1238.93
  5210.5 1238.43  5214.2 1238.43  5214.4 1238.93  5222.5 1242.46  5232.6  1244.3
    5253 1246.37  5318.5 1249.17    5432 1258.39  5436.3 1257.86  5517.1 1263.72
#Mann= 4 ,-1 , 0
  4751.9     .05       0  5210.2     .05       0  5214.4     .05       0
    5432     .12       0
Bank Sta=5210.2,5214.4
XS Rating Curve= 0 ,0
Exp/Cntr=0.3,0.1

Type RM Length L Ch R = 1 ,8500    ,500,500,500
BEGIN DESCRIPTION:
HICKORY05 17.0
END DESCRIPTION:
XS GIS Cut Line= 3
      2736305.68     10244953.12      2735919.69     10245177.76
      2735405.68     10245253.11
#Sta/Elev= 30
  4553.4 1265.74  4598.5 1263.48  4764.8 1251.08  4831.1  1247.4  4876.5 1242.84
  4882.3    1244  4903.8 1243.96    4941 1241.94  4962.5 1241.89  4978.3  1239.5
    4984 1239.74  4993.1 1236.81  4999.4 1236.59  5005.8 1236.77  5014.2 1240.95
  5054.6 1242.04  5070.6 1240.33  5075.6 1240.89    5092 1236.21  5092.5 1235.71
    5098 1236.21  5105.1 1241.67  5115.2 1243.74  5165.8 1243.91  5236.5 1246.43
  5256.7 1248.19  5266.8 1247.72  5405.5 1256.84  5515.2 1264.47  5519.5 1264.65
#Mann= 5 ,-1 , 0
  4553.4     .05       0    5092     .03       0    5098     .05       0
  5405.5     .12       0  5515.2     .05       0
Bank Sta=5092,5098
XS Rating Curve= 0 ,0
Exp/Cntr=0.3,0.1

Type RM Length L Ch R = 1 ,8000    ,500,500,500
BEGIN DESCRIPTION:
HICKORY05 16.0
END DESCRIPTION:
XS GIS Cut Line= 3
      2736105.71     10244653.11      2735840.28      10244698.6
      2735355.71     10245103.09
#Sta/Elev= 30
  4730.7  1256.5  4763.3 1254.99  4811.9 1251.71  4818.2 1250.54  4823.3 1250.96
  4832.2  1250.5    4853 1248.53  4863.5 1247.92  4943.8 1242.44  4964.1 1241.74
  4995.3 1233.84  4995.8 1233.34  5000.8 1233.34  5001.3 1233.84  5013.7 1234.93
    5028  1237.5  5034.5 1237.58  5056.6 1240.19  5091.8 1241.07  5106.5 1240.87
  5167.1 1240.18  5268.8 1241.42  5340.3 1245.12  5346.9 1244.68  5361.2 1245.34
  5403.3 1247.99  5496.5    1253  5580.2 1259.12  5588.9 1259.14  5631.2 1262.47
#Mann= 9 ,-1 , 0
  4730.7     .05       0    4853     .12       0  4863.5     .05       0
  4995.3     .05       0  5001.3     .05       0  5106.5     .12       0
  5167.1     .05       0  5403.3     .12       0  5580.2     .05       0
Bank Sta=4995.3,5001.3
XS Rating Curve= 0 ,0
Exp/Cntr=0.3,0.1

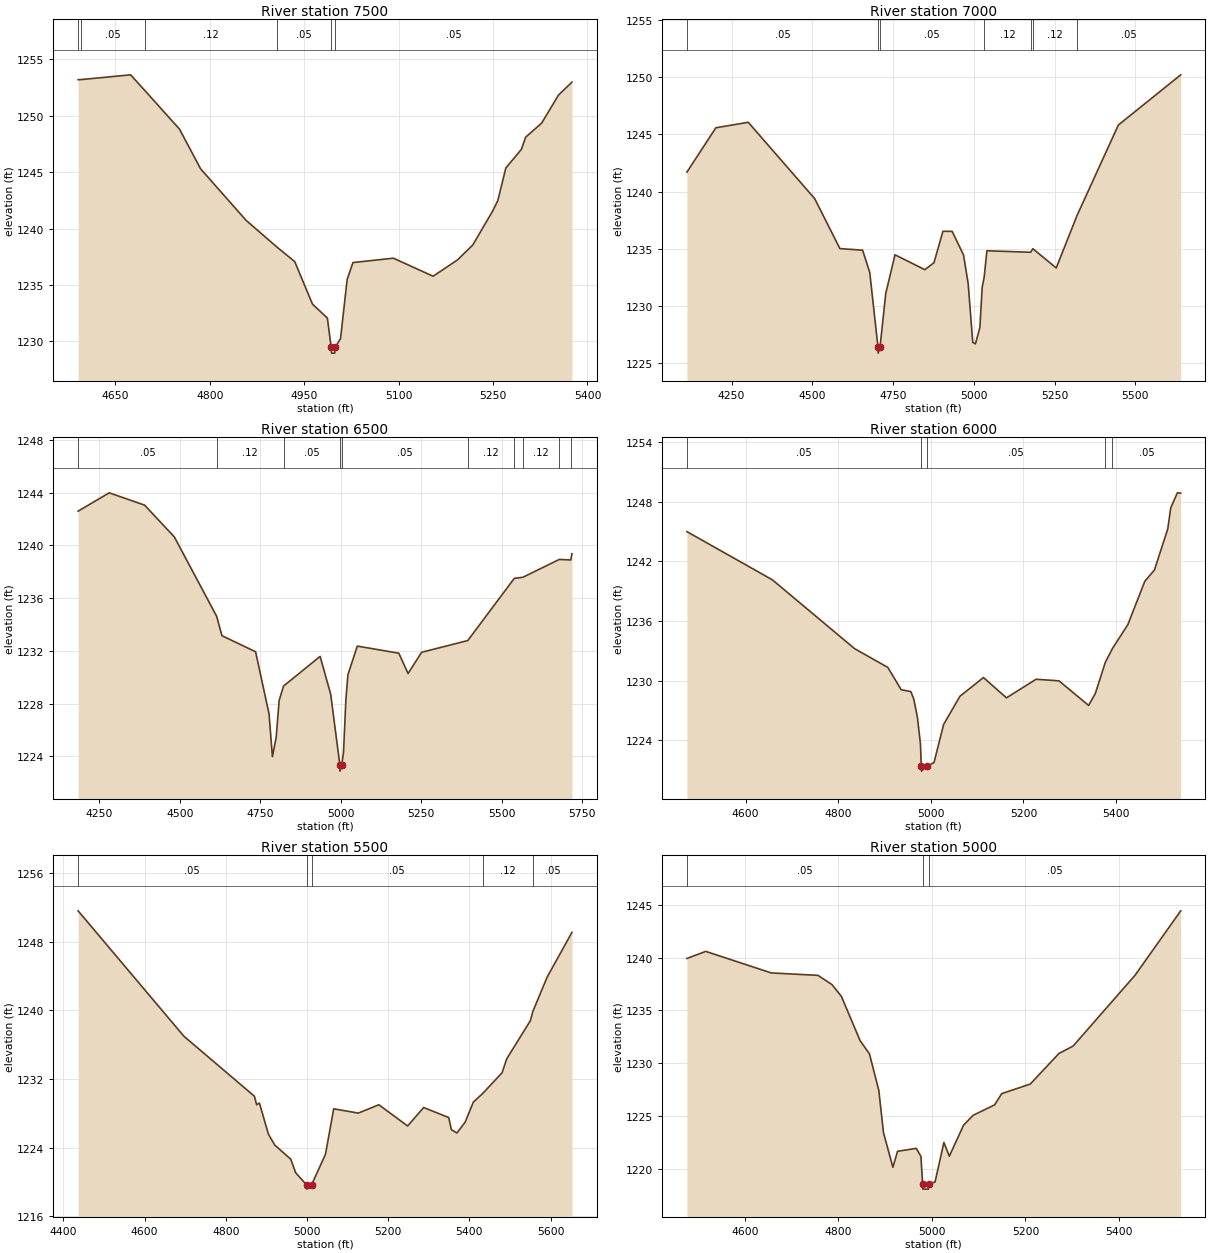
Type RM Length L Ch R = 1 ,7500    ,500,500,500
BEGIN DESCRIPTION:
HICKORY05 15.0
END DESCRIPTION:
XS GIS Cut Line= 3
      2736055.72     10244353.12      2735663.11     10244238.51
      2735305.73      10244353.1
#Sta/Elev= 30
    4591  1253.2    4596 1253.21  4674.4 1253.63  4697.6  1252.2  4752.1 1248.81
  4785.5  1245.3  4857.7 1240.73  4906.7 1238.36    4935 1237.07  4963.3 1233.29
  4986.9 1232.06    4993 1229.45  4993.5 1228.95  4998.6 1228.95  4999.1 1229.45
  5007.8 1230.24  5018.3 1235.49  5027.5 1236.98  5091.7 1237.37  5154.8 1235.77
  5193.4 1237.21  5217.8 1238.54  5249.3 1241.54  5257.6 1242.48  5270.3 1245.37
    5295 1247.02  5301.8  1248.1  5327.2 1249.35    5354 1251.84  5375.3 1252.98
#Mann= 6 ,-1 , 0
    4591     .12       0    4596     .05       0  4697.6     .12       0
  4906.7     .05       0    4993     .05       0  4999.1     .05       0
Bank Sta=4993,4999.1
XS Rating Curve= 0 ,0
Exp/Cntr=0.3,0.1

Type RM Length L Ch R = 1 ,7000    ,500,500,500
BEGIN DESCRIPTION:
HICKORY05 14.0
END DESCRIPTION:
XS GIS Cut Line= 3
      2736253.83     10243254.21      2735570.93     10243822.14
      2735055.68     10244203.11
#Sta/Elev= 30
  4111.8 1241.69  4201.5 1245.56  4301.8 1246.04  4507.5 1239.38  4585.6 1235.02
  4655.9 1234.88    4678 1232.94  4703.6  1226.4  4704.1  1225.9  4709.7  1226.4
  4727.5  1231.1  4756.2 1234.48  4848.6 1233.18  4876.8 1233.79  4904.6 1236.53
  4933.2 1236.52  4968.4 1234.46  4982.7 1231.97  4996.9 1226.84  5005.2 1226.71
    5019 1228.14    5026 1231.63  5032.1  1232.5  5040.7 1234.83  5176.1  1234.7
  5183.1 1235.01  5255.3 1233.33    5320 1237.92  5447.7  1245.8  5640.8 1250.18
#Mann= 7 ,-1 , 0
  4111.8     .05       0  4703.6     .05       0  4709.7     .05       0
  5032.1     .12       0  5176.1     .05       0  5183.1     .12       0
    5320     .05       0
Bank Sta=4703.6,4709.7
XS Rating Curve= 0 ,0
Exp/Cntr=0.3,0.1

Type RM Length L Ch R = 1 ,6500    ,500,500,500
BEGIN DESCRIPTION:
HICKORY05 13.0
END DESCRIPTION:
XS GIS Cut Line= 3
      2736113.24     10243150.03      2735332.34     10243387.82
      2734759.84     10243821.31
#Sta/Elev= 30
  4183.7 1242.59  4280.3 1243.98  4390.2 1243.05  4482.6 1240.64  4614.2 1234.62
  4630.6 1233.15  4735.2 1231.93    4777 1227.21  4787.4 1223.98  4799.1 1225.43
  4808.3 1228.23    4822 1229.33  4935.7 1231.58  4968.5 1228.71  4996.9 1223.38
  4997.4 1222.88    5003 1223.38  5008.3  1224.3  5015.8 1228.34  5022.1 1230.19
  5051.2 1232.36  5180.2 1231.82    5209 1230.28    5251 1231.89  5394.5 1232.78
  5538.8 1237.49  5565.9 1237.58  5678.8 1238.93  5714.5 1238.89  5718.1 1239.36
#Mann= 10 ,-1 , 0
  4183.7     .05       0  4614.2     .12       0    4822     .05       0
  4996.9     .05       0    5003     .05       0  5394.5     .12       0
  5538.8     .05       0  5565.9     .12       0  5678.8     .05       0
  5714.5     .12       0
Bank Sta=4996.9,5003
XS Rating Curve= 0 ,0
Exp/Cntr=0.3,0.1

Type RM Length L Ch R = 1 ,6000    ,500,500,500
BEGIN DESCRIPTION:
HICKORY05 12.0
END DESCRIPTION:
XS GIS Cut Line= 3
      2735555.68     10242603.12      2735146.83     10242935.01
       2734805.7      10243353.1
#Sta/Elev= 30
  4473.4    1245    4658 1240.15  4835.4 1233.23  4907.3 1231.34    4936  1229.1
  4956.9 1228.91  4963.3 1228.15  4971.2  1226.3  4977.7 1223.62  4979.4 1221.41
  4979.9 1220.91  4991.8 1221.41  5006.9 1221.77  5027.7  1225.6  5062.9 1228.44
  5113.7 1230.32  5163.4 1228.28  5227.3 1230.15  5276.8 1229.99  5340.7 1227.52
  5355.1  1228.7  5376.8 1231.85  5392.3 1233.25  5425.4 1235.64  5462.1 1240.01
  5482.9 1241.14  5511.6 1245.27  5518.1  1247.4  5532.4  1248.9  5539.6 1248.87
#Mann= 5 ,-1 , 0
  4473.4     .05       0  4979.4     .03       0  4991.8     .05       0
  5376.8     .12       0  5392.3     .05       0
Bank Sta=4979.4,4991.8
XS Rating Curve= 0 ,0
Exp/Cntr=0.3,0.1

Type RM Length L Ch R = 1 ,5500    ,500,500,500
BEGIN DESCRIPTION:
HICKORY05 11.0
END DESCRIPTION:
XS GIS Cut Line= 3
      2735055.68     10242103.12      2734805.04     10242607.93
      2734705.68     10243253.12
#Sta/Elev= 30
  4436.4 1251.58  4696.9 1236.97  4870.6 1229.98  4876.1 1228.98    4883 1229.18
  4905.3 1225.54  4920.9 1224.28  4960.2 1222.64  4972.3 1221.06    4999 1219.65
  4999.5 1219.15  5011.5 1219.65  5045.7 1223.21    5066 1228.51  5126.7 1228.01
  5177.2 1228.98  5248.1 1226.51  5287.5 1228.66  5349.3 1227.49  5355.7 1226.09
  5369.5 1225.69  5389.7 1226.95    5410  1229.3  5432.7 1230.28  5480.8 1232.72
  5492.2 1234.34  5550.4 1238.78  5556.7 1239.88  5592.1 1243.89  5652.8 1249.07
#Mann= 5 ,-1 , 0
  4436.4     .05       0    4999     .03       0  5011.5     .05       0
  5432.7     .12       0  5556.7     .05       0
Bank Sta=4999,5011.5
XS Rating Curve= 0 ,0
Exp/Cntr=0.3,0.1

Type RM Length L Ch R = 1 ,5000    ,500,500,500
BEGIN DESCRIPTION:
HICKORY05 10.0
END DESCRIPTION:
XS GIS Cut Line= 3
       2734363.2      10242092.8      2734376.29     10242616.63
      2734274.81     10243138.87
#Sta/Elev= 30
    4476 1239.91  4516.3 1240.58  4656.4 1238.54  4756.4 1238.31  4786.4 1237.43
  4806.4 1236.32  4846.4 1232.13  4866.4 1230.88  4886.4 1227.42  4896.4 1223.42
  4916.5 1220.14  4926.5 1221.65  4966.5 1221.93  4976.5 1221.17  4980.1 1218.57
  4980.6 1218.07  4992.4 1218.07  4992.9 1218.57  5006.6 1218.74  5025.6 1222.49
  5037.2 1221.19  5067.7 1224.13  5088.1 1225.06  5134.1 1226.05  5149.2 1227.11
  5210.3 1228.02  5271.5 1230.91    5302 1231.62  5434.5 1238.33    5532 1244.42
#Mann= 3 ,-1 , 0
    4476     .05       0  4980.1     .03       0  4992.9     .05       0
Bank Sta=4980.1,4992.9
XS Rating Curve= 0 ,0
Exp/Cntr=0.3,0.1