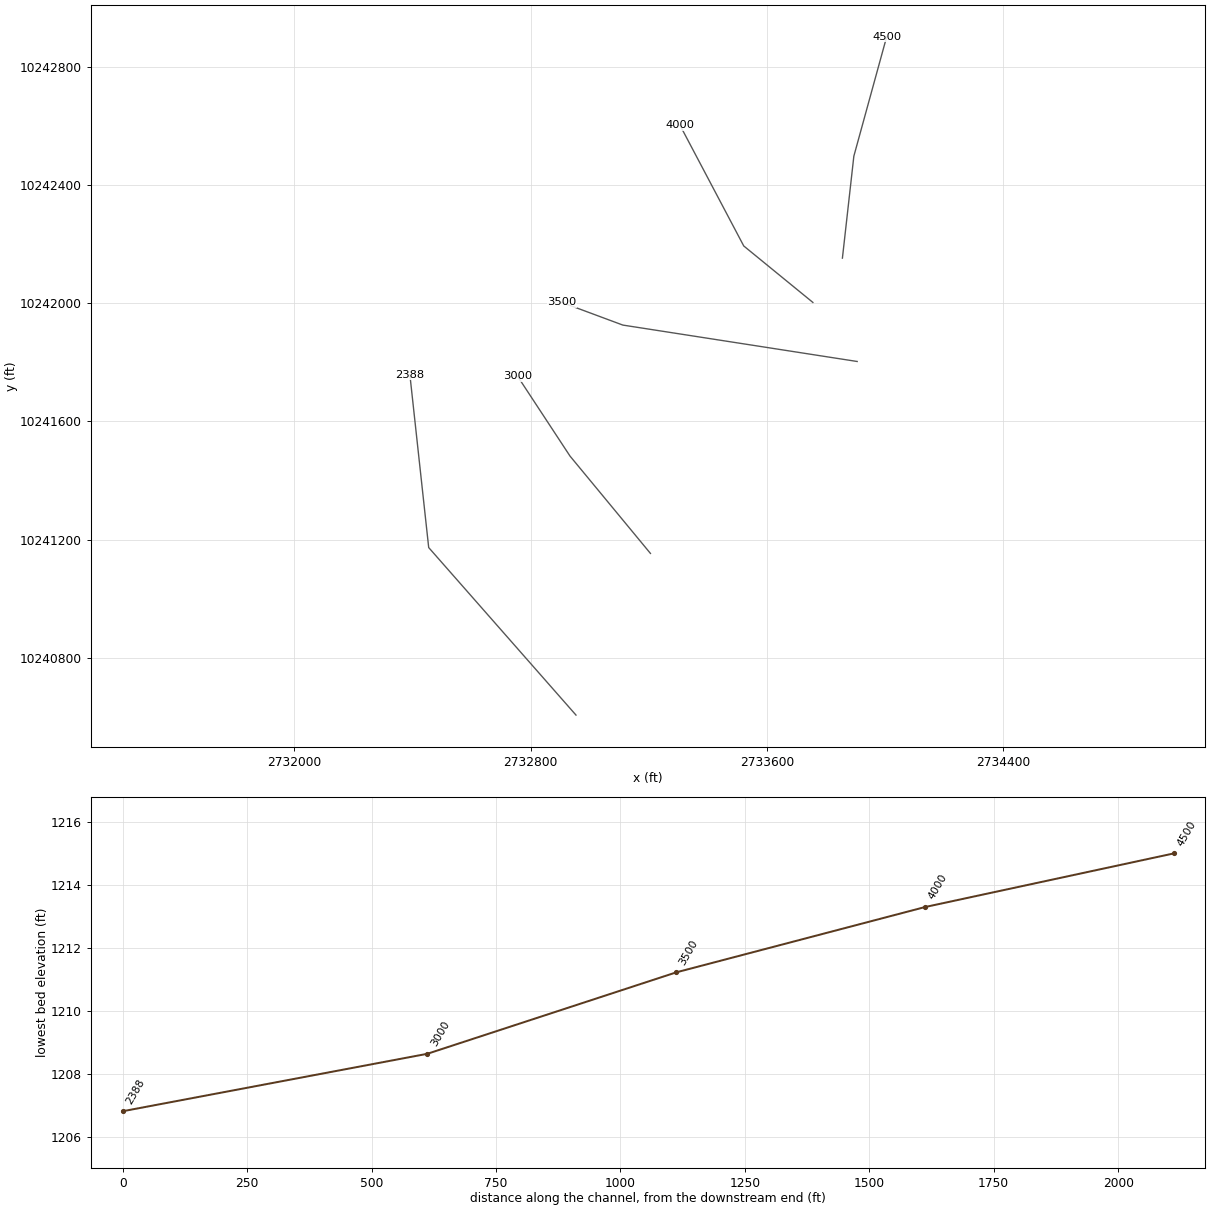
HEC-RAS study HICKORY05.prj: HICKORY05 Base Level Engineering

--- HICKORY05.g01 (geometry) --- (continued)

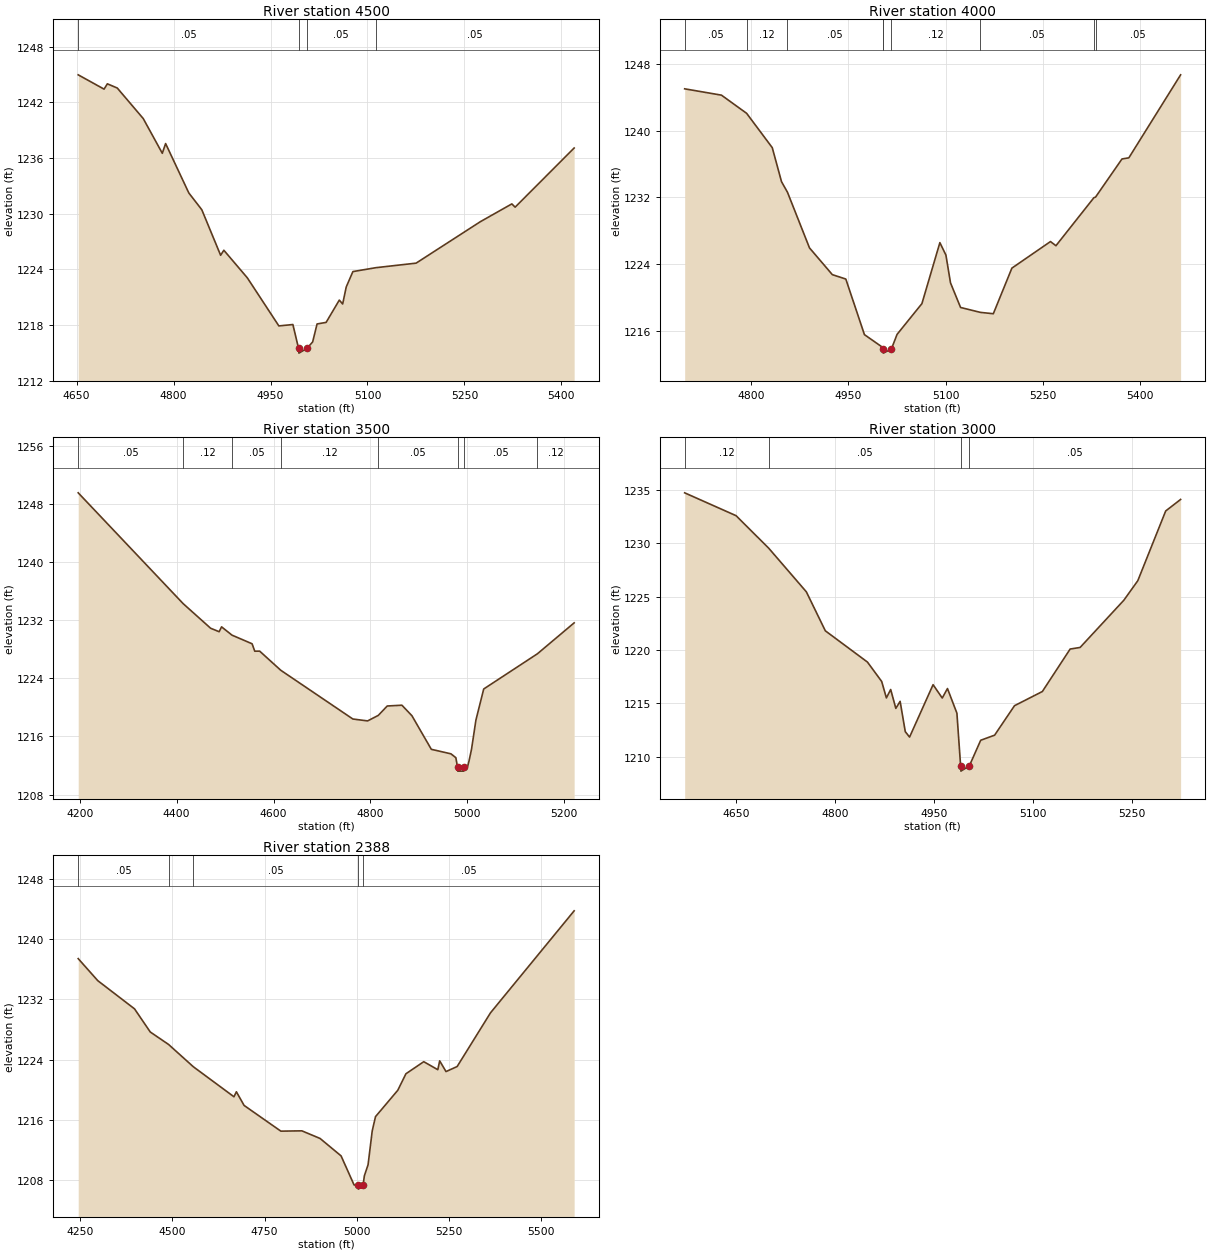
Type RM Length L Ch R = 1 ,4500    ,500,500,500
BEGIN DESCRIPTION:
HICKORY05 9.0
END DESCRIPTION:
XS GIS Cut Line= 3
      2733855.68     10242153.11      2733894.44     10242498.44
      2734005.69     10242903.13
#Sta/Elev= 30
  4652.5 1244.96  4692.5 1243.42  4697.6 1243.99  4712.9 1243.54  4753.1 1240.25
  4782.6 1236.51  4787.7 1237.56  4823.6 1232.24  4843.7 1230.43  4872.8 1225.53
  4877.8 1226.07  4914.1  1223.1  4962.9 1217.92  4984.6 1218.07  4993.4 1215.49
  4993.9 1214.99  5006.2 1215.49  5015.2  1216.2    5022 1218.13    5036  1218.3
  5056.4  1220.7  5061.6 1220.28  5067.1 1222.11  5077.4 1223.77  5112.8 1224.19
  5175.2 1224.68  5274.5 1229.14  5323.3 1231.06  5328.4 1230.71  5419.7 1237.08
#Mann= 4 ,-1 , 0
  4652.5     .05       0  4993.4     .07       0  5006.2     .05       0
  5112.8     .05       0
Bank Sta=4993.4,5006.2
XS Rating Curve= 0 ,0
Exp/Cntr=0.3,0.1

Type RM Length L Ch R = 1 ,4000    ,500,500,500
BEGIN DESCRIPTION:
HICKORY05 8.0
END DESCRIPTION:
XS GIS Cut Line= 3
      2733755.67     10242003.13      2733521.61     10242194.28
      2733305.71     10242603.07
#Sta/Elev= 30
  4697.8 1245.01  4754.5 1244.25  4793.3 1242.07  4832.8 1237.95  4847.1 1233.86
  4856.2 1232.61  4890.2 1225.92  4925.4 1222.71  4946.2 1222.18  4974.9 1215.51
  5002.8 1213.99  5003.5 1213.79    5004 1213.29  5016.5 1213.79  5025.2 1215.54
  5063.5 1219.23  5091.2 1226.55  5100.5 1225.06  5107.6 1221.72  5123.1 1218.77
  5153.7 1218.18  5173.6 1218.02  5202.2 1223.49  5261.7 1226.68  5270.1 1226.18
  5328.6 1231.94  5331.2 1232.02  5371.9 1236.59  5382.5 1236.73  5462.3 1246.69
#Mann= 9 ,-1 , 0
  4697.8     .05       0  4793.3     .12       0  4856.2     .05       0
  5002.8     .12       0  5003.5     .03       0  5016.5     .12       0
  5153.7     .05       0  5328.6     .12       0  5331.2     .05       0
Bank Sta=5003.5,5016.5
XS Rating Curve= 0 ,0
Exp/Cntr=0.3,0.1

Type RM Length L Ch R = 1 ,3500    ,500,500,500
BEGIN DESCRIPTION:
HICKORY05 7.0
END DESCRIPTION:
XS GIS Cut Line= 3
      2733905.69     10241803.11       2733112.2     10241926.38
       2732905.7     10242003.11
#Sta/Elev= 30
    4197 1249.51  4413.6 1234.26  4470.2 1230.88  4487.8  1230.4  4492.8 1231.07
  4514.3 1229.93  4555.8 1228.74  4561.3 1227.72  4571.4 1227.73  4614.9  1225.1
  4763.7 1218.39  4794.1 1218.13  4816.2 1218.89  4834.6 1220.18  4864.9 1220.29
  4885.6 1218.84  4925.6 1214.22  4966.1  1213.6  4976.2 1213.07  4979.8 1211.72
  4980.3 1211.22  4992.4 1211.22  4992.9 1211.72    5000 1211.74  5003.3 1212.59
  5008.6 1214.25  5017.6 1218.24  5033.7 1222.52  5144.4 1227.36  5220.3 1231.62
#Mann= 8 ,-1 , 0
    4197     .05       0  4413.6     .12       0  4514.3     .05       0
  4614.9     .12       0  4816.2     .05       0  4979.8     .03       0
  4992.9     .05       0  5144.4     .12       0
Bank Sta=4979.8,4992.9
XS Rating Curve= 0 ,0
Exp/Cntr=0.3,0.1

Type RM Length L Ch R = 1 ,3000    ,612,612,612
BEGIN DESCRIPTION:
HICKORY05 6.0
END DESCRIPTION:
XS GIS Cut Line= 3
      2733205.68     10241153.12       2732933.3     10241482.74
      2732755.68     10241753.12
#Sta/Elev= 30
  4572.4 1234.72  4650.2 1232.58  4699.7 1229.53  4756.7 1225.44  4785.4 1221.79
  4849.2 1218.86  4870.8 1217.04  4877.9  1215.5  4884.4 1216.29  4892.2 1214.52
  4898.7 1215.18  4906.5 1212.34    4913 1211.83  4948.6 1216.74  4962.5 1215.49
  4970.4 1216.38  4984.7 1214.07  4990.3 1209.14  4990.8 1208.64  5003.6 1209.14
  5020.7 1211.53  5041.8 1212.01  5071.9 1214.77  5114.1  1216.1  5156.2 1220.08
  5171.3 1220.23  5237.6 1224.66  5258.7 1226.49  5300.9 1233.02  5323.5  1234.1
#Mann= 4 ,-1 , 0
  4572.4     .12       0  4699.7     .05       0  4990.3     .03       0
  5003.6     .05       0
Bank Sta=4990.3,5003.6
XS Rating Curve= 0 ,0
Exp/Cntr=0.3,0.1

Type RM Length L Ch R = 1 ,2388    ,0,0,0
BEGIN DESCRIPTION:
HICKORY05 5.0
END DESCRIPTION:
XS GIS Cut Line= 3
      2732953.48     10240605.77      2732454.75       10241173.
        2732391.     10241758.34
#Sta/Elev= 30
  4244.7 1237.39  4297.7 1234.47  4397.3 1230.73    4440 1227.66  4489.5 1226.01
  4556.7 1223.05  4666.8 1219.07  4673.4 1219.73  4694.3 1217.92  4793.9 1214.51
  4850.9 1214.55  4900.2 1213.54  4957.1 1211.23  4992.3 1207.38  5003.5 1207.32
    5004 1206.82  5016.8 1207.32  5020.2 1208.58  5030.3 1210.06  5041.5 1214.53
  5050.4 1216.43  5110.8 1219.93  5132.9 1222.12  5181.2 1223.72  5219.3 1222.66
  5224.4 1223.83  5241.5 1222.41  5271.7 1223.08  5362.2 1230.21  5588.8 1243.73
#Mann= 5 ,-1 , 0
  4244.7     .05       0  4489.5     .12       0  4556.7     .05       0
  5003.5     .03       0  5016.8     .05       0
Bank Sta=5003.5,5016.8
XS Rating Curve= 0 ,0
Exp/Cntr=0.3,0.1

Chan Stop Cuts=-1
Use User Specified Reach Order=0
Composite Channel Slope=5