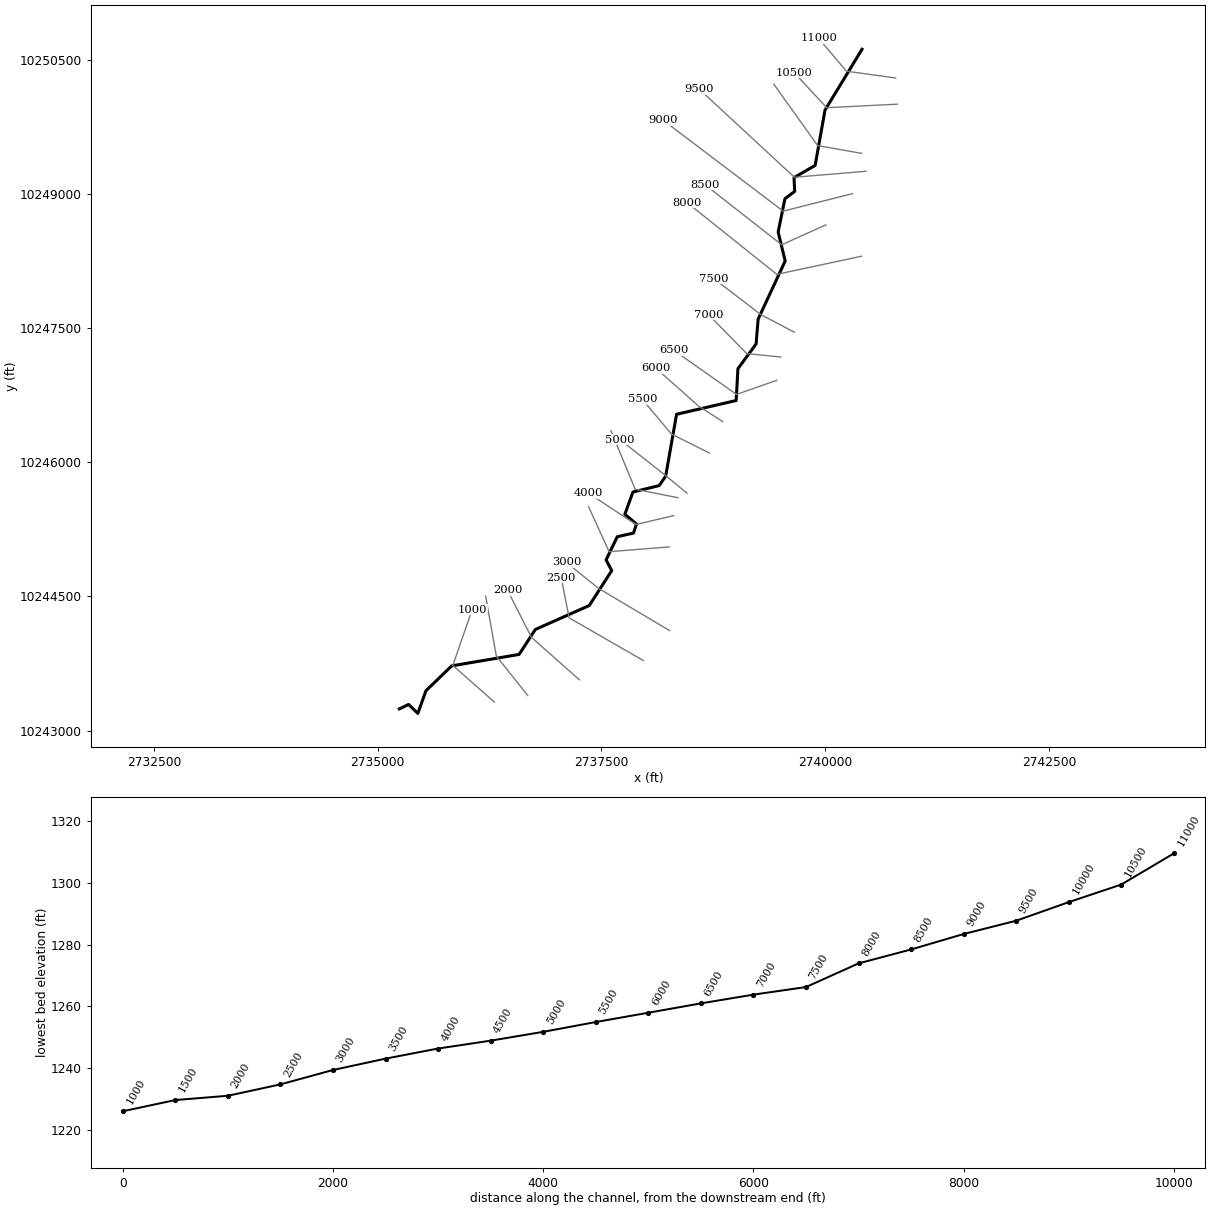
--- HICKORY06.prj (project) ---

Proj Title=HICKORY06 Base Level Engineering
Current Plan=p01
Default Exp/Contr=0.3,0.1
English Units
Geom File=g01
Flow File=f01
Plan File=p01
BEGIN DESCRIPTION:
HICKORY06
END DESCRIPTION:

--- HICKORY06.p01 (plan) ---

Plan Title=Multiple Run
Short Identifier=Multiple
Geom File=g01
Flow File=f01
Subcritical Flow
K Sum by GR= 0
Std Step Tol= 0.01
Critical Tol= 0.01
Num of Std Step Trials= 20
Max Error Tol= 0.3
Flow Tol Ratio= 0.001
Split Flow NTrial= 30
Split Flow Tol= 0.02
Split Flow Ratio= 0.02
Log Output Level= 0
Friction Slope Method= 1
Unsteady Friction Slope Method= 2
Unsteady Bridges Friction Slope Method= 1
Parabolic Critical Depth
Global Vel Dist=  1 , 1 , 1
Global Log Level= 0
CheckData=True
Encroach Param= -1, 0, 0, 0
BEGIN DESCRIPTION:
Multiple Run
END DESCRIPTION:

--- HICKORY06.f01 (steady flow) ---

Flow Title=Multiple
Number of Profiles=7
Profile Names=10-year,25-year,50-year,1pct_min,100-year,1pct_plu,500-year
River Rch & RM= HICKORY06,Reach-1,11000
     487     789    1036     794    1374    2378    1861
River Rch & RM= HICKORY06,Reach-1,2500
     575     945    1193     874    1587    2881    2147
Boundary for River Rch & Prof#=HICKORY06,Reach-1,1
Up Type=0
Dn Type=3
Dn Slope=0.005
Boundary for River Rch & Prof#=HICKORY06,Reach-1,2
Up Type=0
Dn Type=3
Dn Slope=0.005
Boundary for River Rch & Prof#=HICKORY06,Reach-1,3
Up Type=0
Dn Type=3
Dn Slope=0.005
Boundary for River Rch & Prof#=HICKORY06,Reach-1,4
Up Type=0
Dn Type=3
Dn Slope=0.005
Boundary for River Rch & Prof#=HICKORY06,Reach-1,5
Up Type=0
Dn Type=3
Dn Slope=0.005
Boundary for River Rch & Prof#=HICKORY06,Reach-1,6
Up Type=0
Dn Type=3
Dn Slope=0.005
Boundary for River Rch & Prof#=HICKORY06,Reach-1,7
Up Type=0
Dn Type=3
Dn Slope=0.005

--- HICKORY06.g01 (geometry) ---

Geom Title=Existing Conditions

River Reach=HICKORY06,Reach-1
Reach XY= 30
      2740410.75     10250617.00      2739997.50     10249937.00
      2739887.00     10249318.00      2739651.00     10249182.00
      2739658.50     10249028.00      2739549.50     10248946.00
      2739474.00     10248574.00      2739552.50     10248250.00
      2739250.00     10247599.00      2739227.50     10247322.00
      2739024.50     10247046.00      2739004.75     10246690.00
      2738339.00     10246536.00      2738217.25     10245845.00
      2738145.25     10245739.00      2737851.50     10245667.00
      2737761.25     10245418.00      2737891.25     10245309.00
      2737857.75     10245208.00      2737676.50     10245167.00
      2737551.50     10244908.00      2737614.50     10244788.00
      2737364.00     10244398.00      2736761.00     10244130.00
      2736579.75     10243851.00      2735826.50     10243723.00
      2735539.00     10243445.00      2735448.50     10243192.00
      2735345.25     10243292.00      2735241.75     10243242.00

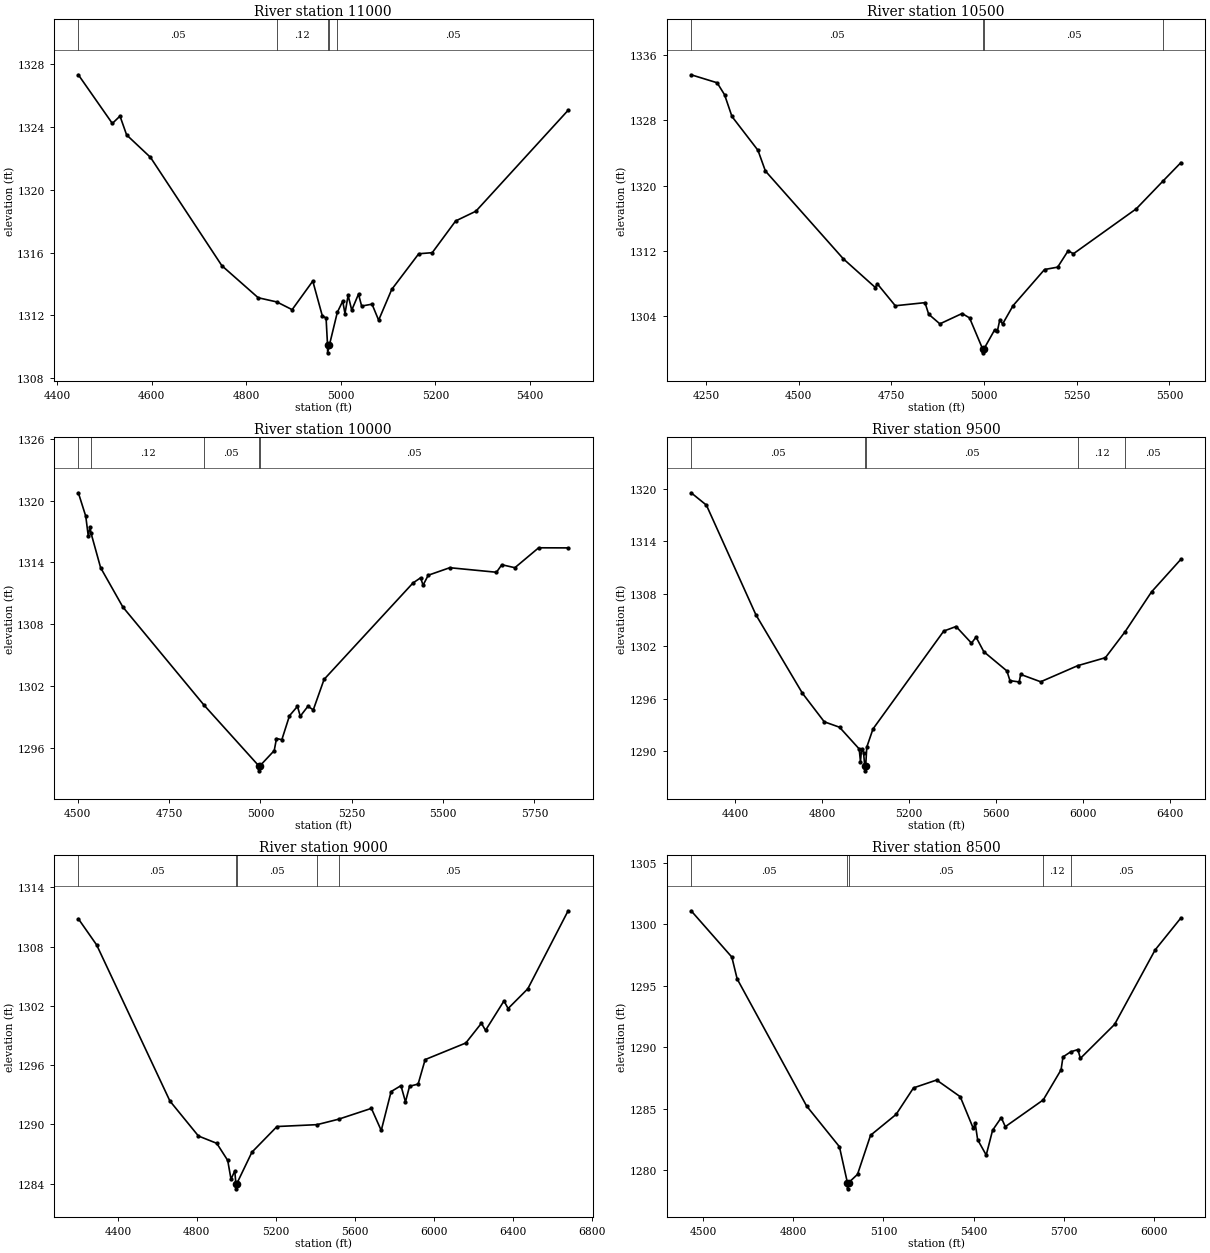
Type RM Length L Ch R = 1,11000,500,500,500
BEGIN DESCRIPTION:
HICKORY06 22.0
END DESCRIPTION:
XS GIS Cut Line= 3
      2740786.86     10250295.87      2740236.90     10250371.99
      2739926.60     10250739.25
#Sta/Elev= 30
  4444.8 1327.32  4516.7 1324.22  4532.9 1324.69  4546.9 1323.49  4597.4 1322.06
  4748.4 1315.16  4825.2 1313.12  4864.8 1312.85  4897.0 1312.36  4940.7 1314.18
  4960.9 1311.96  4968.8 1311.83  4971.9 1310.11  4972.1 1309.61  4975.9 1310.11
  4992.6 1312.19  5004.0 1312.90  5008.8 1312.11  5015.4 1313.27  5023.1 1312.33
  5037.4 1313.35  5044.0 1312.59  5066.0 1312.71  5080.0 1311.69  5107.7 1313.65
  5164.8 1315.92  5193.4 1315.99  5242.9 1318.01  5285.7 1318.63  5480.8 1325.06
#Mann=5,-1,0
  4444.8    0.05       0  4864.8    0.12       0  4971.9    0.05       0
  4975.9    0.12       0  4992.6    0.05       0
Bank Sta=4971.9,4975.9
Exp/Cntr=0.3,0.1

Type RM Length L Ch R = 1,10500,500,500,500
BEGIN DESCRIPTION:
HICKORY06 21.0
END DESCRIPTION:
XS GIS Cut Line= 3
      2740805.69     10250003.11      2740016.49     10249963.48
      2739655.71     10250353.09
#Sta/Elev= 30
  4209.8 1333.59  4279.9 1332.61  4299.9 1331.15  4319.9 1328.48  4390.0 1324.34
  4410.1 1321.80  4620.3 1311.04  4706.8 1307.52  4711.8 1307.99  4760.5 1305.29
  4840.6 1305.67  4850.6 1304.25  4880.7 1303.07  4940.7 1304.34  4960.8 1303.80
  4995.9 1300.02  4996.1 1299.52  4999.9 1300.02  5028.4 1302.33  5035.8 1302.17
  5042.6 1303.60  5049.9 1303.05  5078.3 1305.31  5163.1 1309.73  5198.5 1310.02
  5226.8 1312.03  5241.0 1311.66  5410.6 1317.17  5483.5 1320.61  5531.0 1322.83
#Mann=4,-1,0
  4209.8    0.05       0  4995.9    0.03       0  4999.9    0.05       0
  5483.5    0.12       0
Bank Sta=4995.9,4999.9
Exp/Cntr=0.3,0.1

Type RM Length L Ch R = 1,10000,500,500,500
BEGIN DESCRIPTION:
HICKORY06 20.0
END DESCRIPTION:
XS GIS Cut Line= 3
      2740405.71     10249453.11      2739914.84     10249540.55
      2739425.72     10250226.41
#Sta/Elev= 30
  4501.4 1320.75  4521.7 1318.48  4528.4 1316.61  4533.5 1317.42  4536.4 1316.81
  4562.4 1313.49  4623.3 1309.68  4845.7 1300.17  4995.0 1294.31  4995.3 1293.81
  4999.0 1294.31  5037.7 1295.77  5043.9 1296.94  5058.6 1296.83  5079.5 1299.15
  5101.4 1300.06  5109.0 1299.10  5129.9 1300.06  5144.7 1299.72  5174.2 1302.67
  5417.6 1312.01  5438.4 1312.51  5445.3 1311.80  5459.3 1312.76  5518.4 1313.49
  5646.2 1313.05  5660.9 1313.78  5696.6 1313.49  5761.7 1315.42  5842.4 1315.41
#Mann=5,-1,0
  4501.4    0.05       0  4536.4    0.12       0  4845.7    0.05       0
  4995.0    0.05       0  4999.0    0.05       0
Bank Sta=4995,4999
Exp/Cntr=0.3,0.1

Type RM Length L Ch R = 1,9500,500,500,500
BEGIN DESCRIPTION:
HICKORY06 19.0
END DESCRIPTION:
XS GIS Cut Line= 3
      2740455.65     10249253.11      2739655.35     10249186.14
      2738592.38     10250170.87
#Sta/Elev= 30
  4196.9 1319.53  4267.1 1318.12  4494.8 1305.59  4708.6 1296.64  4809.0 1293.38
  4879.2 1292.76  4969.6 1290.28  4975.5 1288.83  4980.5 1290.27  4989.6 1289.87
  4995.3 1288.28  4995.6 1287.78  4999.3 1288.28  5004.6 1290.50  5033.0 1292.56
  5358.4 1303.74  5415.1 1304.26  5486.0 1302.36  5507.0 1303.05  5542.7 1301.38
  5648.7 1299.19  5662.9 1298.08  5705.4 1297.93  5712.2 1298.79  5804.1 1297.95
  5974.6 1299.79  6101.7 1300.70  6192.4 1303.67  6313.7 1308.21  6449.0 1311.94
#Mann=5,-1,0
  4196.9    0.05       0  4995.3    0.05       0  4999.3    0.05       0
  5974.6    0.12       0  6192.4    0.05       0
Bank Sta=4995.3,4999.3
Exp/Cntr=0.3,0.1

Type RM Length L Ch R = 1,9000,500,500,500
BEGIN DESCRIPTION:
HICKORY06 18.0
END DESCRIPTION:
XS GIS Cut Line= 3
      2740305.66     10249003.11      2739529.82     10248807.19
      2738190.13     10249823.24
#Sta/Elev= 30
  4199.8 1310.82  4292.6 1308.17  4663.9 1292.36  4808.3 1288.82  4901.1 1288.08
  4956.6 1286.35  4973.3 1284.45  4992.5 1285.29  4998.0 1283.97  4998.3 1283.47
  5002.0 1283.97  5079.2 1287.18  5206.2 1289.78  5409.3 1289.97  5518.0 1290.52
  5684.6 1291.62  5734.5 1289.38  5784.5 1293.32  5834.4 1293.92  5857.2 1292.28
  5878.0 1293.86  5921.4 1294.08  5957.0 1296.56  6163.0 1298.24  6242.0 1300.24
  6262.9 1299.52  6356.4 1302.50  6377.3 1301.73  6477.1 1303.73  6681.4 1311.63
#Mann=5,-1,0
  4199.8    0.05       0  4998.0    0.03       0  5002.0    0.05       0
  5409.3    0.12       0  5518.0    0.05       0
Bank Sta=4998,5002
Exp/Cntr=0.3,0.1

Type RM Length L Ch R = 1,8500,500,500,500
BEGIN DESCRIPTION:
HICKORY06 17.0
END DESCRIPTION:
XS GIS Cut Line= 3
      2740005.67     10248653.10      2739513.81     10248431.20
      2738655.67     10249103.12
#Sta/Elev= 30
  4460.4 1301.10  4595.8 1297.33  4613.5 1295.55  4844.4 1285.21  4953.7 1281.89
  4980.3 1278.96  4980.6 1278.46  4984.3 1278.96  5013.9 1279.64  5057.3 1282.82
  5142.3 1284.52  5200.2 1286.68  5277.1 1287.32  5355.7 1285.96  5399.1 1283.38
  5405.4 1283.80  5413.6 1282.46  5442.1 1281.21  5463.3 1283.23  5492.2 1284.26
  5505.6 1283.52  5631.8 1285.70  5691.1 1288.15  5697.5 1289.20  5722.8 1289.61
  5747.2 1289.80  5755.3 1289.08  5869.3 1291.85  6004.0 1297.91  6089.9 1300.52
#Mann=5,-1,0
  4460.4    0.05       0  4980.3    0.03       0  4984.3    0.05       0
  5631.8    0.12       0  5722.8    0.05       0
Bank Sta=4980.3,4984.3
Exp/Cntr=0.3,0.1

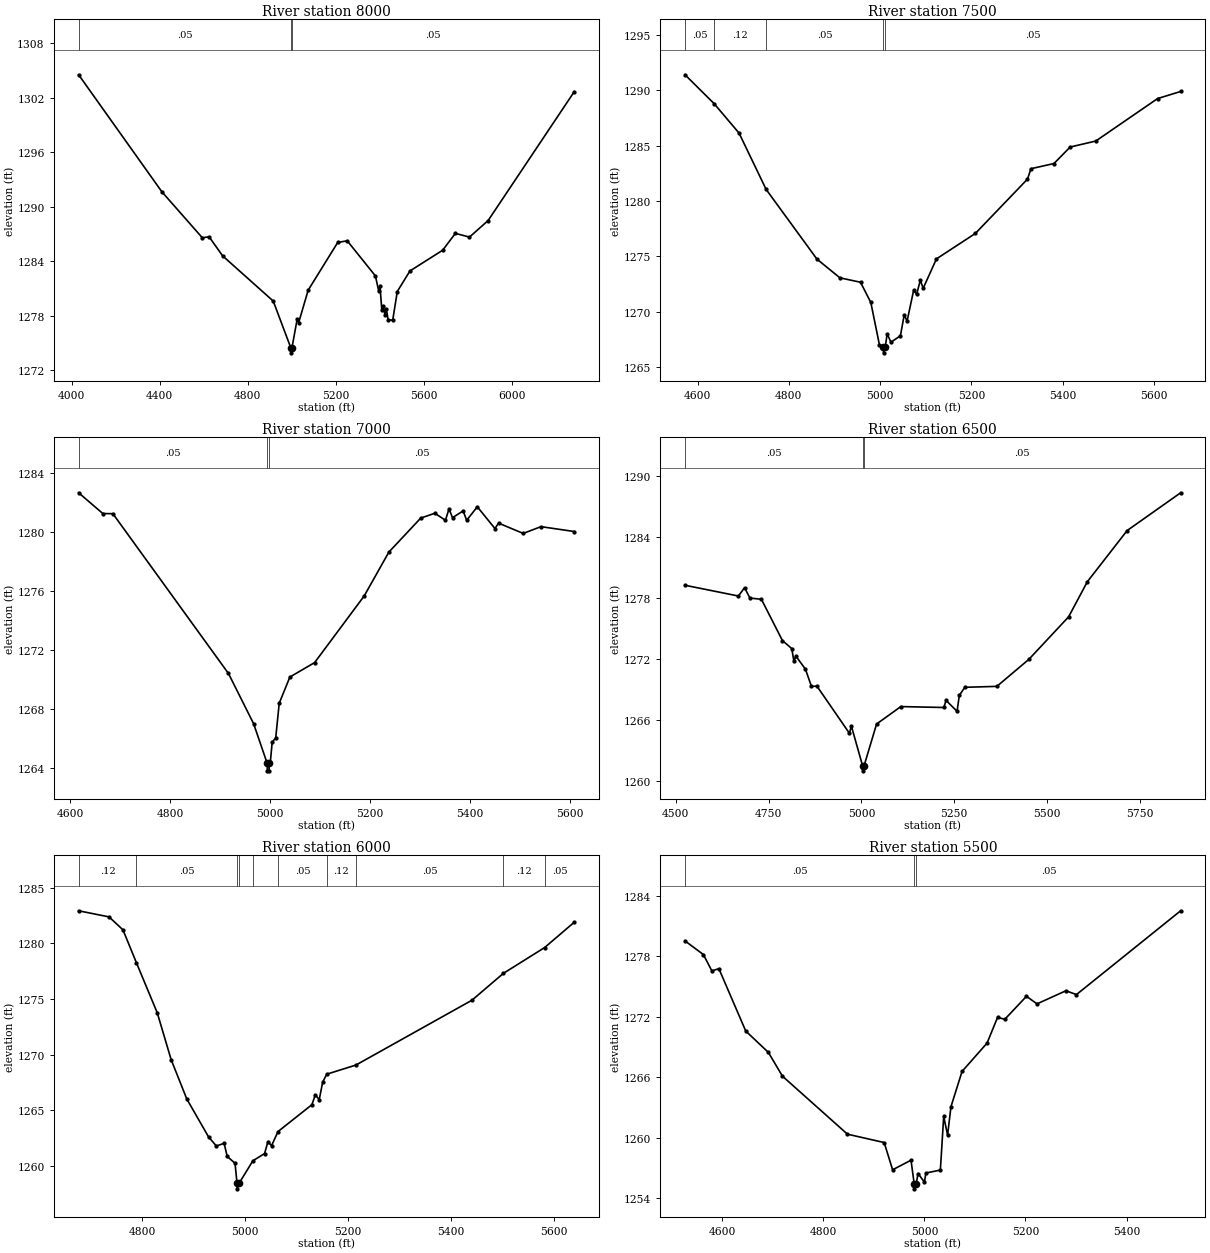
Type RM Length L Ch R = 1,8000,500,500,500
BEGIN DESCRIPTION:
HICKORY06 16.0
END DESCRIPTION:
XS GIS Cut Line= 3
      2740405.70     10248303.12      2739458.91     10248100.63
      2738455.68     10248903.11
#Sta/Elev= 30
  4031.8 1304.50  4410.2 1291.64  4594.3 1286.58  4624.7 1286.70  4686.3 1284.60
  4916.4 1279.63  4997.1 1274.44  4997.3 1273.94  5001.1 1274.44  5025.7 1277.70
  5032.1 1277.27  5075.3 1280.83  5209.8 1286.08  5253.0 1286.25  5381.0 1282.39
  5395.5 1280.77  5401.9 1281.24  5409.9 1278.67  5416.3 1279.12  5424.3 1278.09
  5430.7 1278.75  5438.7 1277.59  5459.5 1277.52  5480.3 1280.68  5537.9 1282.94
  5686.8 1285.22  5744.4 1287.07  5808.5 1286.66  5893.3 1288.48  6284.7 1302.64
#Mann=3,-1,0
  4031.8    0.05       0  4997.1    0.05       0  5001.1    0.05       0
Bank Sta=4997.1,5001.1
Exp/Cntr=0.3,0.1

Type RM Length L Ch R = 1,7500,500,500,500
BEGIN DESCRIPTION:
HICKORY06 15.0
END DESCRIPTION:
XS GIS Cut Line= 3
      2739655.66     10247453.12      2739277.66     10247652.38
      2738755.66     10248053.13
#Sta/Elev= 30
  4572.7 1291.40  4636.2 1288.80  4691.0 1286.13  4750.3 1281.04  4861.6 1274.74
  4911.8 1273.05  4957.0 1272.65  4979.6 1270.82  4998.3 1267.02  5007.1 1266.77
  5007.4 1266.27  5011.1 1266.77  5015.4 1267.99  5023.6 1267.23  5044.4 1267.81
  5052.7 1269.70  5059.0 1269.14  5073.5 1271.95  5079.8 1271.55  5088.0 1272.82
  5094.3 1272.11  5123.3 1274.76  5208.5 1277.06  5322.7 1281.97  5330.3 1282.91
  5380.7 1283.38  5416.1 1284.87  5472.2 1285.41  5607.6 1289.25  5658.1 1289.89
#Mann=5,-1,0
  4572.7    0.05       0  4636.2    0.12       0  4750.3    0.05       0
  5007.1    0.03       0  5011.1    0.05       0
Bank Sta=5007.1,5011.1
Exp/Cntr=0.3,0.1

Type RM Length L Ch R = 1,7000,500,500,500
BEGIN DESCRIPTION:
HICKORY06 14.0
END DESCRIPTION:
XS GIS Cut Line= 3
      2739503.79     10247176.09      2739122.63     10247214.54
      2738697.50     10247649.06
#Sta/Elev= 30
  4616.9 1282.69  4665.3 1281.28  4685.4 1281.27  4916.5 1270.42  4966.8 1267.01
  4994.0 1264.31  4994.2 1263.81  4997.7 1263.81  4998.0 1264.31  5000.0 1264.31
  5003.9 1265.75  5011.0 1266.05  5018.0 1268.40  5039.3 1270.18  5088.8 1271.16
  5187.8 1275.68  5237.2 1278.66  5300.9 1280.97  5329.2 1281.30  5350.4 1280.82
  5357.5 1281.60  5364.5 1281.00  5385.8 1281.46  5392.8 1280.82  5414.1 1281.74
  5449.4 1280.26  5456.5 1280.63  5505.9 1279.93  5541.4 1280.39  5607.9 1280.06
#Mann=3,-1,0
  4616.9    0.05       0  4994.0    0.05       0  4998.0    0.05       0
Bank Sta=4994,4998
Exp/Cntr=0.3,0.1

Type RM Length L Ch R = 1,6500,500,500,500
BEGIN DESCRIPTION:
HICKORY06 13.0
END DESCRIPTION:
XS GIS Cut Line= 3
      2739456.94     10246915.66      2739008.80     10246757.89
      2738305.70     10247253.10
#Sta/Elev= 30
  4524.9 1279.25  4668.7 1278.19  4685.3 1279.01  4699.7 1277.99  4730.6 1277.87
  4787.3 1273.80  4812.5 1273.01  4818.2 1271.75  4823.5 1272.27  4849.2 1270.99
  4865.5 1269.28  4880.1 1269.32  4967.7 1264.67  4973.0 1265.38  5003.2 1261.47
  5003.4 1260.97  5007.2 1261.47  5040.9 1265.58  5106.2 1267.30  5222.0 1267.21
  5228.1 1267.91  5257.7 1266.83  5263.8 1268.40  5278.6 1269.20  5364.9 1269.29
  5451.1 1271.95  5558.2 1276.14  5608.7 1279.60  5715.9 1284.64  5860.0 1288.36
#Mann=3,-1,0
  4524.9    0.05       0  5003.2    0.03       0  5007.2    0.05       0
Bank Sta=5003.2,5007.2
Exp/Cntr=0.3,0.1

Type RM Length L Ch R = 1,6000,500,500,500
BEGIN DESCRIPTION:
HICKORY06 12.0
END DESCRIPTION:
XS GIS Cut Line= 3
      2738855.71     10246453.09      2738584.32     10246628.42
      2738105.67     10247053.12
#Sta/Elev= 30
  4676.9 1282.92  4736.0 1282.37  4763.0 1281.21  4789.1 1278.26  4829.7 1273.75
  4856.7 1269.54  4887.1 1266.01  4929.3 1262.61  4944.5 1261.79  4959.6 1262.03
  4965.6 1260.85  4980.8 1260.24  4984.7 1258.44  4985.0 1257.94  4988.7 1258.44
  5015.5 1260.46  5038.2 1261.11  5044.8 1262.19  5051.7 1261.81  5064.4 1263.09
  5130.2 1265.50  5136.8 1266.39  5144.4 1265.95  5151.1 1267.53  5159.0 1268.24
  5215.7 1269.06  5441.3 1274.89  5502.3 1277.30  5582.5 1279.62  5639.9 1281.89
#Mann=10,-1,0
  4676.9    0.12       0  4789.1    0.05       0  4984.7    0.05       0
  4988.7    0.05       0  5015.5    0.12       0  5064.4    0.05       0
  5159.0    0.12       0  5215.7    0.05       0  5502.3    0.12       0
  5582.5    0.05       0
Bank Sta=4984.7,4988.7
Exp/Cntr=0.3,0.1

Type RM Length L Ch R = 1,5500,500,500,500
BEGIN DESCRIPTION:
HICKORY06 11.0
END DESCRIPTION:
XS GIS Cut Line= 3
      2738705.65     10246103.13      2738281.97     10246314.99
      2737955.65     10246703.15
#Sta/Elev= 30
  4526.3 1279.50  4562.6 1278.15  4579.4 1276.53  4593.3 1276.75  4646.4 1270.57
  4691.2 1268.45  4719.1 1266.09  4847.7 1260.34  4920.4 1259.51  4937.1 1256.81
  4973.5 1257.76  4979.8 1255.42  4980.1 1254.92  4983.8 1255.42  4987.4 1256.44
  5000.0 1255.59  5003.0 1256.49  5031.6 1256.78  5038.2 1262.10  5045.9 1260.24
  5052.5 1263.05  5074.5 1266.56  5124.0 1269.37  5144.8 1271.92  5159.1 1271.73
  5202.0 1274.01  5222.9 1273.26  5280.1 1274.56  5300.9 1274.18  5507.1 1282.49
#Mann=3,-1,0
  4526.3    0.05       0  4979.8    0.03       0  4983.8    0.05       0
Bank Sta=4979.8,4983.8
Exp/Cntr=0.3,0.1

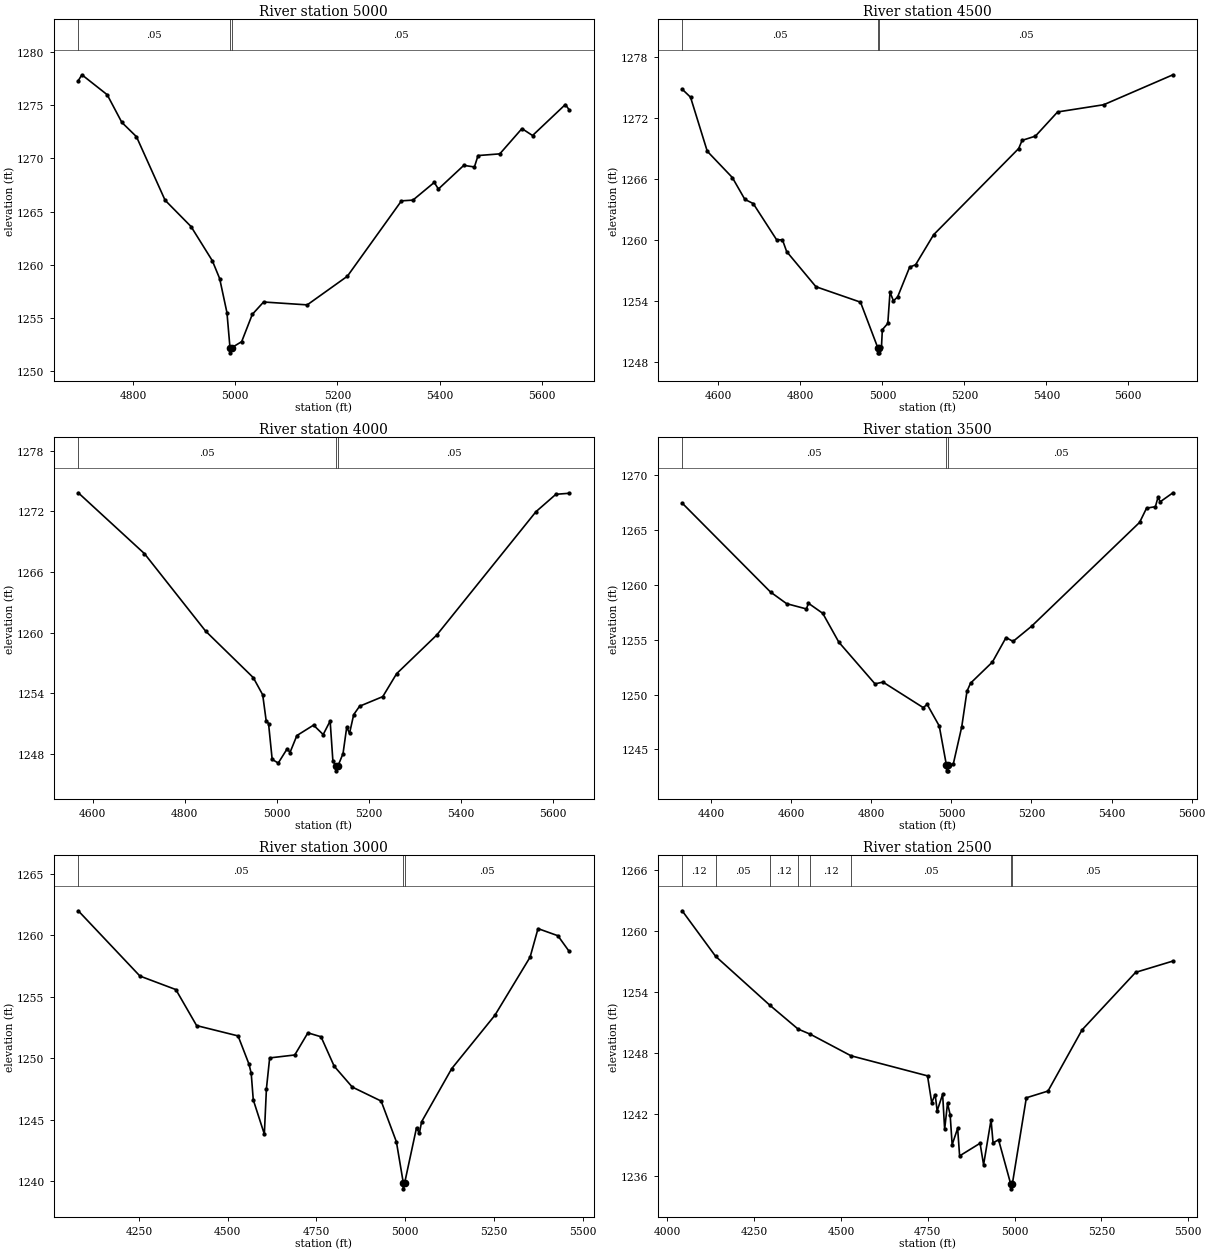
Type RM Length L Ch R = 1,5000,500,500,500
BEGIN DESCRIPTION:
HICKORY06 10.0
END DESCRIPTION:
XS GIS Cut Line= 3
      2738455.67     10245653.12      2738219.20     10245849.37
      2737705.71     10246253.09
#Sta/Elev= 30
  4692.7 1277.28  4699.8 1277.83  4749.3 1275.96  4778.0 1273.36  4806.6 1272.02
  4862.6 1266.06  4913.4 1263.59  4955.1 1260.38  4969.4 1258.71  4983.7 1255.51
  4989.6 1252.24  4989.8 1251.74  4993.6 1252.24  5012.5 1252.79  5033.3 1255.35
  5055.4 1256.51  5140.8 1256.24  5219.4 1258.93  5325.2 1266.00  5347.7 1266.07
  5389.4 1267.73  5397.5 1267.11  5447.2 1269.33  5468.0 1269.18  5475.1 1270.25
  5517.7 1270.41  5561.0 1272.78  5581.8 1272.13  5646.0 1275.04  5653.2 1274.56
#Mann=3,-1,0
  4692.7    0.05       0  4989.6    0.05       0  4993.6    0.05       0
Bank Sta=4989.6,4993.6
Exp/Cntr=0.3,0.1

Type RM Length L Ch R = 1,4500,500,500,500
BEGIN DESCRIPTION:
HICKORY06 9.0
END DESCRIPTION:
XS GIS Cut Line= 3
      2738355.70     10245603.11      2737876.64     10245698.16
      2737605.68     10246353.13
#Sta/Elev= 30
  4511.6 1274.84  4532.0 1274.05  4572.8 1268.73  4634.0 1266.14  4664.5 1263.99
  4684.9 1263.58  4741.9 1260.02  4756.3 1260.00  4766.5 1258.85  4837.9 1255.39
  4946.6 1253.87  4988.8 1249.38  4989.0 1248.88  4992.5 1248.88  4992.8 1249.38
  4997.8 1249.49  4999.9 1251.16  5013.2 1251.78  5018.6 1254.85  5027.0 1254.00
  5037.1 1254.38  5066.4 1257.31  5081.1 1257.56  5125.0 1260.51  5332.5 1269.00
  5340.8 1269.80  5373.3 1270.22  5427.4 1272.60  5539.9 1273.31  5708.8 1276.26
#Mann=3,-1,0
  4511.6    0.05       0  4988.8    0.03       0  4992.8    0.05       0
Bank Sta=4988.8,4992.8
Exp/Cntr=0.3,0.1

Type RM Length L Ch R = 1,4000,500,500,500
BEGIN DESCRIPTION:
HICKORY06 8.0
END DESCRIPTION:
XS GIS Cut Line= 3
      2738305.73     10245403.12      2737885.73     10245303.28
      2737355.67     10245653.12
#Sta/Elev= 30
  4568.3 1273.83  4712.2 1267.81  4845.1 1260.15  4948.7 1255.55  4969.2 1253.85
  4976.7 1251.30  4981.9 1251.01  4989.8 1247.46  5003.0 1247.10  5022.5 1248.52
  5028.5 1248.14  5043.5 1249.82  5079.7 1250.85  5100.7 1249.92  5115.8 1251.26
  5121.8 1247.29  5128.9 1246.83  5129.1 1246.33  5132.9 1246.83  5143.8 1248.03
  5151.9 1250.67  5157.9 1250.03  5167.0 1251.89  5179.8 1252.72  5230.2 1253.67
  5260.3 1255.94  5347.5 1259.76  5563.2 1271.96  5606.5 1273.68  5635.1 1273.78
#Mann=3,-1,0
  4568.3    0.05       0  5128.9    0.03       0  5132.9    0.05       0
Bank Sta=5128.9,5132.9
Exp/Cntr=0.3,0.1

Type RM Length L Ch R = 1,3500,500,500,500
BEGIN DESCRIPTION:
HICKORY06 7.0
END DESCRIPTION:
XS GIS Cut Line= 3
      2738255.72     10245053.11      2737585.35     10244999.67
      2737355.70     10245503.07
#Sta/Elev= 30
  4327.5 1267.46  4548.2 1259.35  4588.4 1258.29  4637.8 1257.81  4642.8 1258.33
  4678.6 1257.41  4718.8 1254.78  4809.1 1250.98  4829.1 1251.14  4929.4 1248.82
  4939.5 1249.10  4969.6 1247.14  4987.6 1243.55  4987.9 1243.05  4991.4 1243.05
  4991.6 1243.55  5004.6 1243.66  5025.8 1247.07  5038.8 1250.30  5047.7 1251.04
  5102.4 1252.97  5136.4 1255.20  5154.0 1254.85  5200.1 1256.23  5470.0 1265.70
  5487.4 1267.00  5509.4 1267.13  5516.0 1267.99  5521.5 1267.58  5553.3 1268.40
#Mann=3,-1,0
  4327.5    0.05       0  4987.6    0.03       0  4991.6    0.05       0
Bank Sta=4987.6,4991.6
Exp/Cntr=0.3,0.1

Type RM Length L Ch R = 1,3000,500,500,500
BEGIN DESCRIPTION:
HICKORY06 6.0
END DESCRIPTION:
XS GIS Cut Line= 3
      2738259.05     10244118.79      2737467.70     10244589.57
      2737108.01     10244879.20
#Sta/Elev= 30
  4079.2 1261.99  4252.9 1256.68  4354.1 1255.58  4412.6 1252.65  4529.4 1251.81
  4560.2 1249.51  4566.4 1248.77  4572.2 1246.61  4603.4 1243.82  4609.3 1247.53
  4618.4 1250.02  4689.1 1250.26  4726.1 1252.06  4763.1 1251.74  4800.1 1249.35
  4851.1 1247.65  4932.5 1246.51  4975.4 1243.20  4994.8 1239.87  4995.1 1239.37
  4998.8 1239.87  5032.1 1244.34  5040.1 1243.89  5046.5 1244.83  5131.3 1249.15
  5252.9 1253.49  5352.1 1258.22  5374.4 1260.54  5430.4 1259.96  5461.8 1258.70
#Mann=3,-1,0
  4079.2    0.05       0  4994.8    0.03       0  4998.8    0.05       0
Bank Sta=4994.8,4998.8
Exp/Cntr=0.3,0.1

Type RM Length L Ch R = 1,2500,500,500,500
BEGIN DESCRIPTION:
HICKORY06 5.0
END DESCRIPTION:
XS GIS Cut Line= 3
      2737967.88     10243782.43      2737138.45     10244259.81
      2737050.71     10244707.29
#Sta/Elev= 30
  4043.0 1261.97  4139.1 1257.51  4295.3 1252.71  4376.7 1250.37  4412.1 1249.86
  4529.0 1247.75  4749.4 1245.78  4761.4 1243.16  4771.4 1243.94  4777.1 1242.35
  4792.9 1243.97  4798.7 1240.53  4807.0 1243.10  4814.5 1241.97  4820.3 1239.03
  4836.1 1240.63  4841.8 1237.93  4900.7 1239.17  4910.8 1237.06  4932.3 1241.47
  4938.1 1239.20  4953.9 1239.52  4988.7 1235.20  4989.1 1234.70  4993.7 1235.20
  5033.9 1243.63  5096.3 1244.29  5194.1 1250.28  5348.5 1255.93  5456.0 1257.04
#Mann=8,-1,0
  4043.0    0.12       0  4139.1    0.05       0  4295.3    0.12       0
  4376.7    0.05       0  4412.1    0.12       0  4529.0    0.05       0
  4988.7    0.03       0  4993.7    0.05       0
Bank Sta=4988.7,4993.7
Exp/Cntr=0.3,0.1

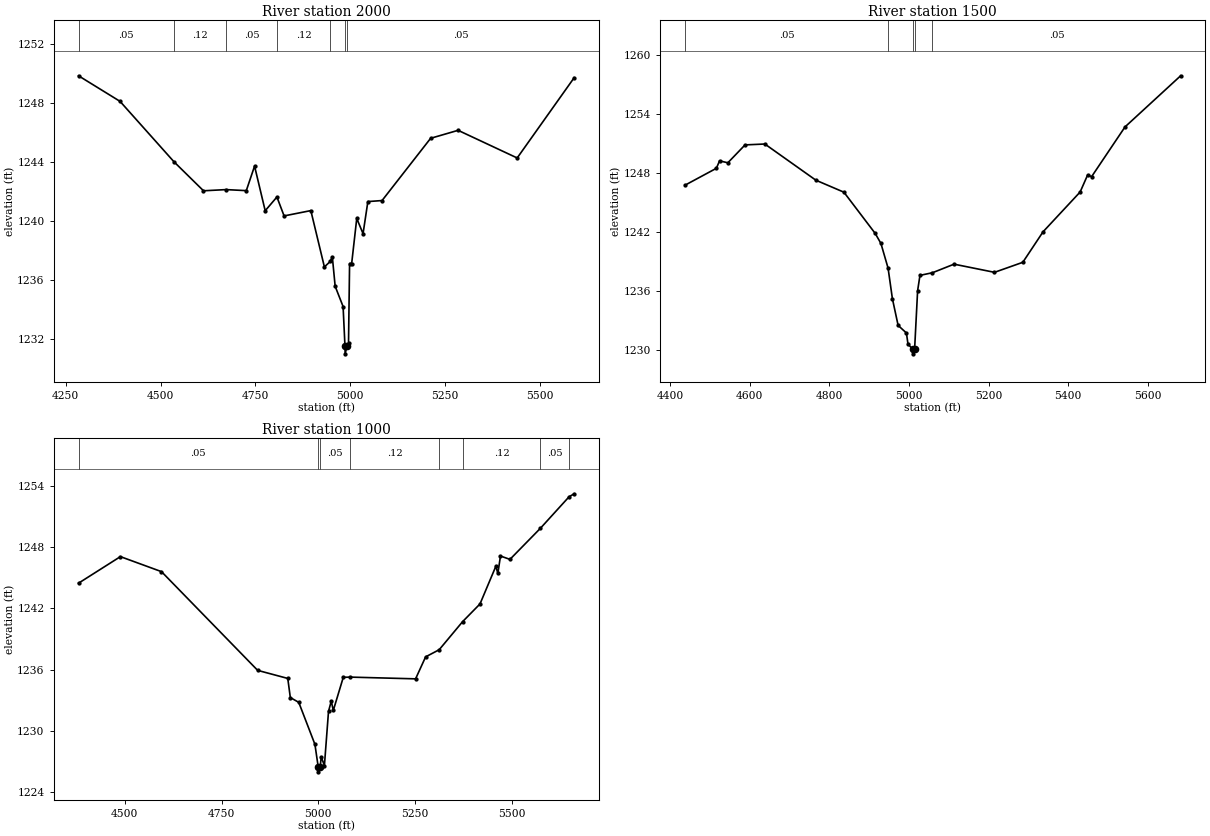
Type RM Length L Ch R = 1,2000,500,500,500
BEGIN DESCRIPTION:
HICKORY06 4.0
END DESCRIPTION:
XS GIS Cut Line= 3
      2737253.83     10243566.70      2736717.76     10244041.94
      2736450.59     10244567.87
#Sta/Elev= 30
  4283.6 1249.82  4393.0 1248.09  4535.3 1244.00  4613.0 1242.04  4672.6 1242.12
  4725.8 1242.05  4747.6 1243.71  4775.6 1240.69  4806.5 1241.62  4825.4 1240.34
  4895.9 1240.70  4931.6 1236.89  4947.1 1237.26  4952.5 1237.58  4960.0 1235.58
  4980.9 1234.21  4985.9 1231.51  4986.3 1231.01  4991.0 1231.51  4995.2 1231.71
  4998.0 1237.12  5003.5 1237.12  5016.9 1240.17  5033.5 1239.14  5046.2 1241.31
  5083.6 1241.38  5211.6 1245.59  5284.0 1246.13  5439.7 1244.26  5589.9 1249.69
#Mann=7,-1,0
  4283.6    0.05       0  4535.3    0.12       0  4672.6    0.05       0
  4806.5    0.12       0  4947.1    0.05       0  4985.9    0.03       0
  4991.0    0.05       0
Bank Sta=4985.9,4991
Exp/Cntr=0.3,0.1

Type RM Length L Ch R = 1,1500,500,500,500
BEGIN DESCRIPTION:
HICKORY06 3.0
END DESCRIPTION:
XS GIS Cut Line= 3
      2736676.45     10243392.29      2736325.74     10243831.43
      2736205.69     10244503.09
#Sta/Elev= 30
  4438.0 1246.77  4516.8 1248.49  4524.8 1249.25  4545.6 1249.05  4588.8 1250.87
  4638.5 1250.96  4766.6 1247.28  4837.0 1246.06  4915.5 1241.87  4929.9 1240.85
  4947.9 1238.33  4958.7 1235.23  4973.1 1232.51  4993.9 1231.74  4997.9 1230.60
  5009.3 1230.12  5009.7 1229.62  5014.5 1230.12  5022.0 1236.03  5027.9 1237.60
  5059.3 1237.87  5113.5 1238.74  5215.0 1237.91  5286.1 1238.93  5336.9 1242.03
  5430.0 1246.08  5448.7 1247.80  5458.8 1247.64  5542.7 1252.70  5682.3 1257.90
#Mann=5,-1,0
  4438.0    0.05       0  4947.9    0.12       0  5009.3    0.07       0
  5014.5    0.12       0  5059.3    0.05       0
Bank Sta=5009.3,5014.5
Exp/Cntr=0.3,0.1

Type RM Length L Ch R = 1,1000,0,0,0
BEGIN DESCRIPTION:
HICKORY06 2.0
END DESCRIPTION:
XS GIS Cut Line= 3
      2736303.97     10243318.31      2735839.09     10243728.09
      2736055.69     10244353.12
#Sta/Elev= 30
  4380.3 1244.45  4488.6 1247.05  4594.8 1245.58  4843.4 1235.92  4921.2 1235.13
  4927.8 1233.26  4949.6 1232.79  4991.4 1228.68  4999.8 1226.49  5000.2 1225.99
  5005.1 1226.49  5007.7 1227.47  5015.9 1226.59  5026.5 1231.90  5033.6 1232.91
  5038.9 1232.00  5064.7 1235.24  5082.5 1235.26  5251.6 1235.09  5277.5 1237.24
  5312.6 1237.94  5373.2 1240.69  5418.1 1242.42  5459.0 1246.10  5464.3 1245.41
  5471.0 1247.11  5495.5 1246.78  5573.9 1249.81  5648.4 1252.91  5661.5 1253.20
#Mann=8,-1,0
  4380.3    0.05       0  4999.8    0.05       0  5005.1    0.05       0
  5082.5    0.12       0  5312.6    0.05       0  5373.2    0.12       0
  5573.9    0.05       0  5648.4    0.12       0
Bank Sta=4999.8,5005.1
Exp/Cntr=0.3,0.1

Chan Stop Cuts=-1