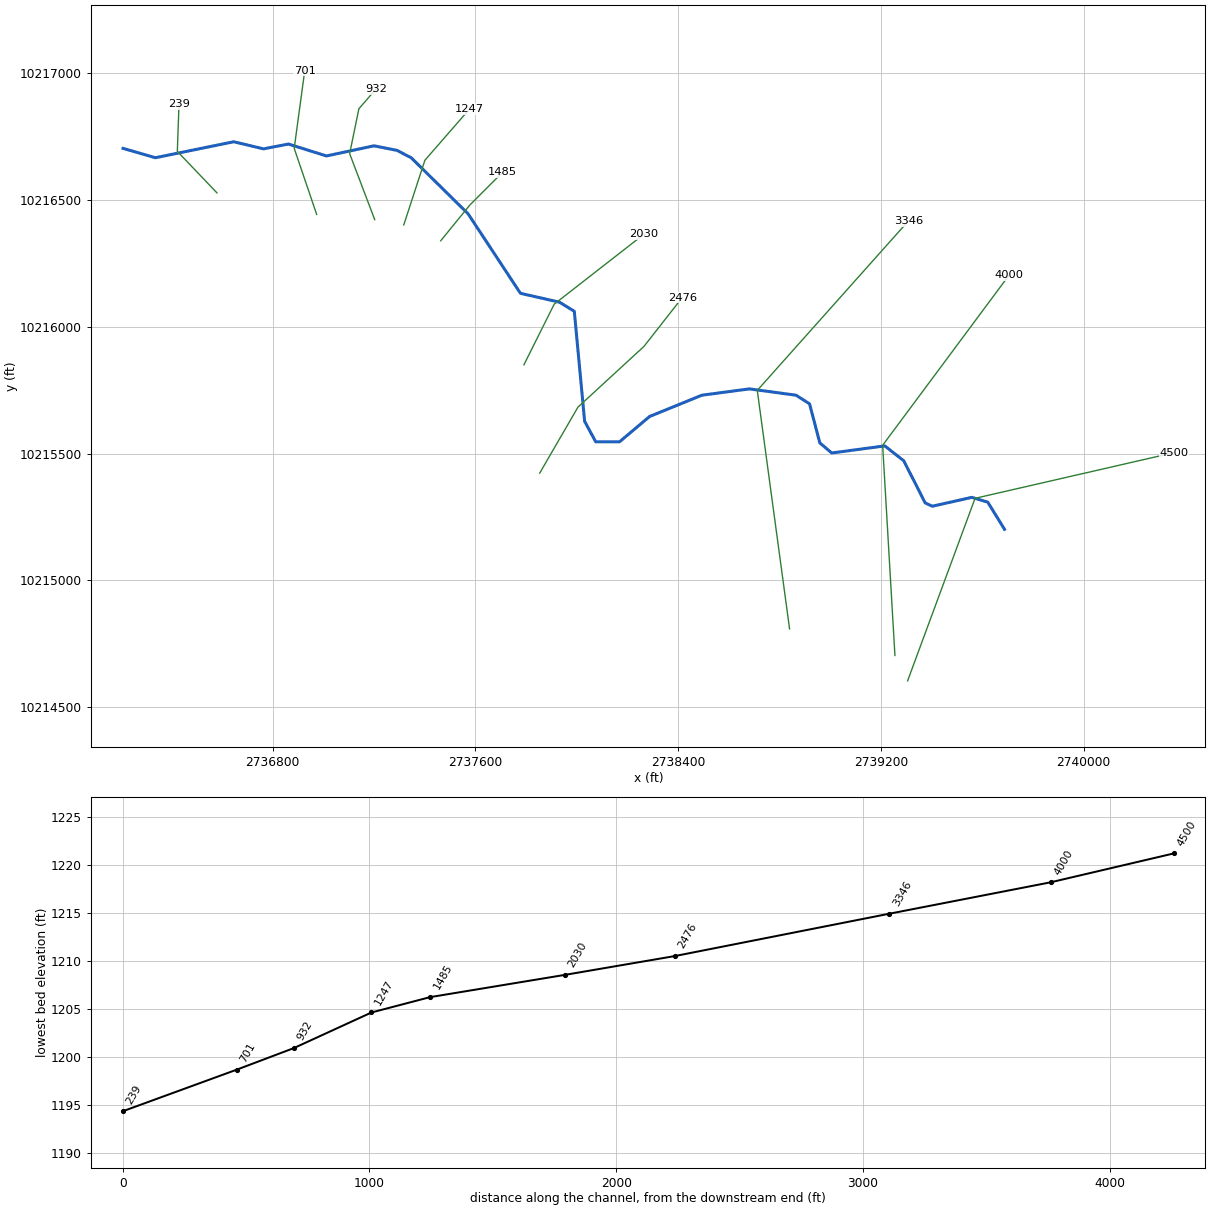
--- HICKORY11.prj (project) ---

Proj Title=HICKORY11 Base Level Engineering
Current Plan=p01
Default Exp/Contr=0.3,0.1
English Units
Geom File=g01
Flow File=f01
Plan File=p01
BEGIN DESCRIPTION:
HICKORY11
END DESCRIPTION:

--- HICKORY11.p01 (plan) ---

Plan Title=Multiple Run
Short Identifier=Multiple
Geom File=g01
Flow File=f01
Subcritical Flow
K Sum by GR= 0
Std Step Tol= 0.01
Critical Tol= 0.01
Num of Std Step Trials= 20
Max Error Tol= 0.3
Flow Tol Ratio= 0.001
Split Flow NTrial= 30
Split Flow Tol= 0.02
Split Flow Ratio= 0.02
Log Output Level= 0
Friction Slope Method= 1
Unsteady Friction Slope Method= 2
Unsteady Bridges Friction Slope Method= 1
Parabolic Critical Depth
Global Vel Dist=  1 , 1 , 1
Global Log Level= 0
CheckData=True
Encroach Param= -1, 0, 0, 0
BEGIN DESCRIPTION:
Multiple Run
END DESCRIPTION:

--- HICKORY11.f01 (steady flow) ---

Flow Title=Multiple
Number of Profiles=7
Profile Names=10-year,25-year,50-year,1pct_min,100-year,1pct_plu,500-year
River Rch & RM= HICKORY11,Reach-1,4500
     341     542     596     376     657    1148     866
River Rch & RM= HICKORY11,Reach-1,1485
     503     817     893     659    1159    2036    1533
Boundary for River Rch & Prof#=HICKORY11,Reach-1,1
Up Type=0
Dn Type=3
Dn Slope=0.005
Boundary for River Rch & Prof#=HICKORY11,Reach-1,2
Up Type=0
Dn Type=3
Dn Slope=0.005
Boundary for River Rch & Prof#=HICKORY11,Reach-1,3
Up Type=0
Dn Type=3
Dn Slope=0.005
Boundary for River Rch & Prof#=HICKORY11,Reach-1,4
Up Type=0
Dn Type=3
Dn Slope=0.005
Boundary for River Rch & Prof#=HICKORY11,Reach-1,5
Up Type=0
Dn Type=3
Dn Slope=0.005
Boundary for River Rch & Prof#=HICKORY11,Reach-1,6
Up Type=0
Dn Type=3
Dn Slope=0.005
Boundary for River Rch & Prof#=HICKORY11,Reach-1,7
Up Type=0
Dn Type=3
Dn Slope=0.005

--- HICKORY11.g01 (geometry) ---

Geom Title=Existing Conditions

River Reach=HICKORY11,Reach-1
Reach XY= 30
      2739688.00     10215201.00      2739622.00     10215308.00
      2739559.25     10215327.00      2739403.25     10215292.00
      2739375.00     10215305.00      2739290.75     10215471.00
      2739215.75     10215530.00      2739006.25     10215502.00
      2738959.25     10215542.00      2738918.75     10215696.00
      2738865.50     10215730.00      2738681.25     10215755.00
      2738493.75     10215730.00      2738287.50     10215646.00
      2738168.75     10215546.00      2738075.00     10215546.00
      2738031.25     10215627.00      2737990.50     10216061.00
      2737932.25     10216097.00      2737778.00     10216132.00
      2737571.25     10216446.00      2737346.75     10216667.00
      2737290.75     10216696.00      2737200.00     10216714.00
      2737012.50     10216674.00      2736862.50     10216721.00
      2736764.00     10216702.00      2736646.75     10216730.00
      2736337.50     10216667.00      2736209.75     10216704.00

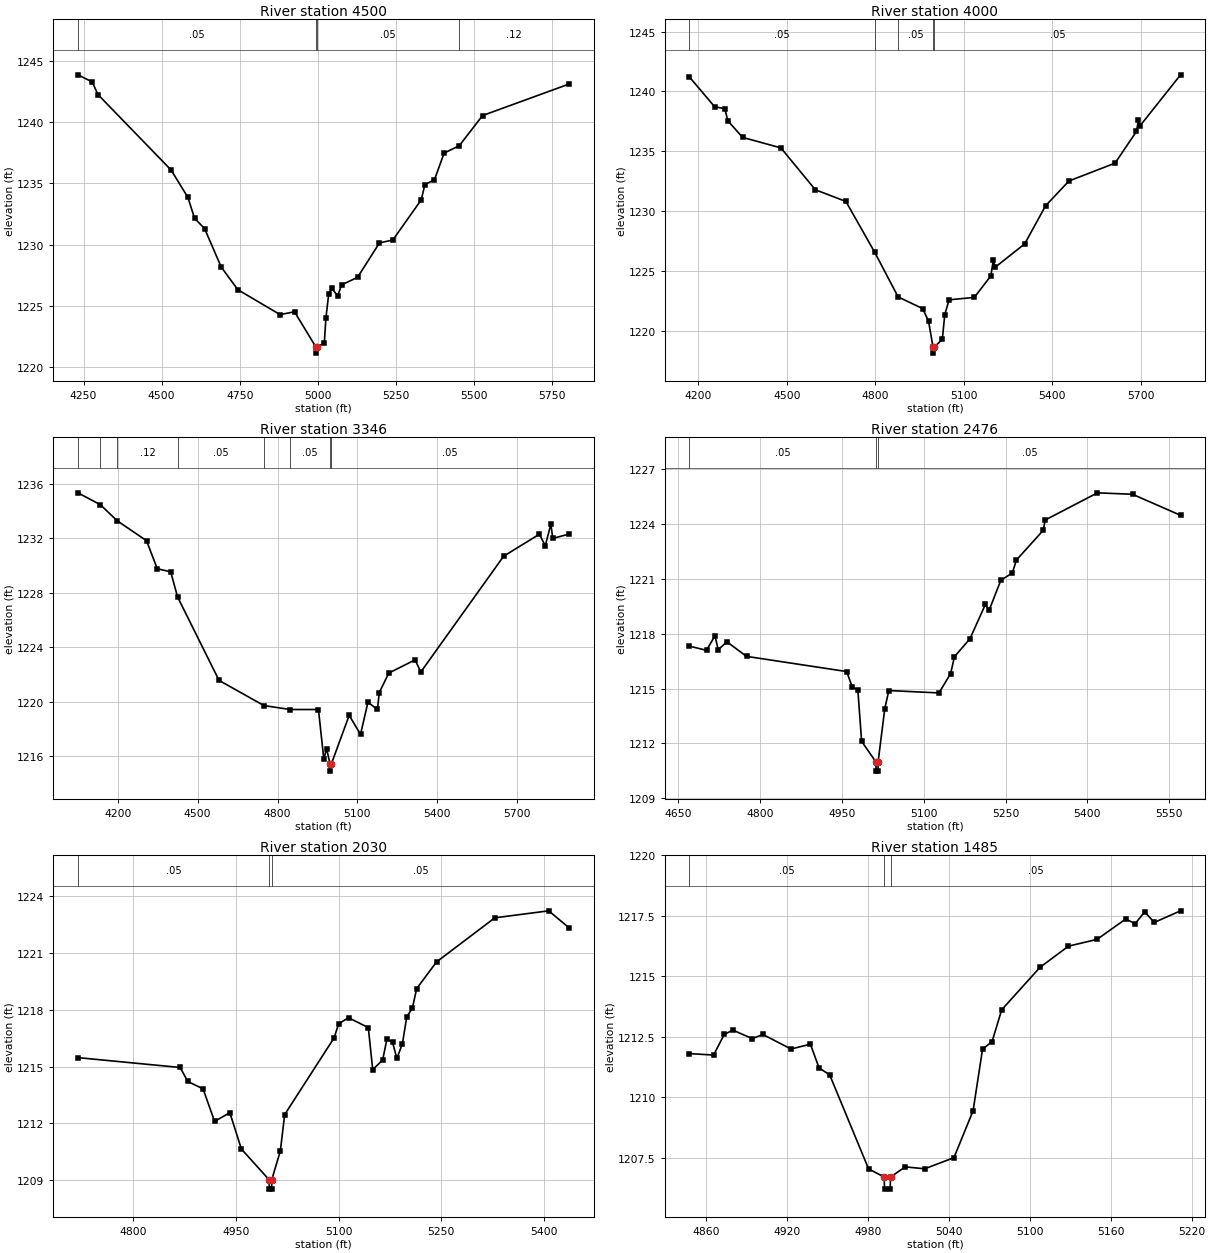
Type RM Length L Ch R = 1,4500,500,500,500
BEGIN DESCRIPTION:
HICKORY11 9.0
END DESCRIPTION:
XS GIS Cut Line= 3
      2739305.68     10214603.10      2739571.82     10215323.19
      2740355.64     10215503.10
#Sta/Elev= 30
  4232.3 1243.86  4277.9 1243.28  4296.3 1242.25  4530.3 1236.10  4584.1 1233.87
  4605.5 1232.16  4637.4 1231.33  4690.7 1228.19  4744.0 1226.34  4879.3 1224.31
  4925.3 1224.54  4993.7 1221.67  4993.9 1221.17  4997.7 1221.67  5020.7 1222.00
  5025.8 1224.02  5034.7 1225.99  5045.0 1226.44  5063.5 1225.84  5075.8 1226.73
  5127.1 1227.35  5197.3 1230.16  5239.9 1230.39  5331.0 1233.67  5342.5 1234.91
  5373.3 1235.31  5404.1 1237.48  5452.6 1238.08  5527.2 1240.54  5804.2 1243.11
#Mann=4,-1,0
  4232.3    0.05       0  4993.7    0.03       0  4997.7    0.05       0
  5452.6    0.12       0
Bank Sta=4993.7,4997.7
Exp/Cntr=0.3,0.1

Type RM Length L Ch R = 1,4000,654,654,654
BEGIN DESCRIPTION:
HICKORY11 8.0
END DESCRIPTION:
XS GIS Cut Line= 3
      2739255.68     10214703.16      2739207.19     10215532.44
      2739705.66     10216203.08
#Sta/Elev= 30
  4169.3 1241.21  4254.7 1238.73  4289.5 1238.56  4299.5 1237.56  4349.6 1236.17
  4479.8 1235.29  4596.3 1231.80  4700.2 1230.82  4798.3 1226.56  4877.4 1222.85
  4960.6 1221.88  4980.6 1220.83  4995.8 1218.66  4996.1 1218.16  4999.8 1218.66
  5027.3 1219.31  5035.7 1221.38  5050.3 1222.61  5135.8 1222.81  5192.1 1224.61
  5200.2 1225.91  5206.7 1225.33  5306.8 1227.28  5377.7 1230.46  5457.0 1232.53
  5613.5 1234.02  5686.1 1236.67  5692.7 1237.62  5699.0 1237.16  5835.6 1241.39
#Mann=5,-1,0
  4169.3    0.05       0  4798.3    0.12       0  4877.4    0.05       0
  4995.8    0.03       0  4999.8    0.05       0
Bank Sta=4995.8,4999.8
Exp/Cntr=0.3,0.1

Type RM Length L Ch R = 1,3346,870,870,870
BEGIN DESCRIPTION:
HICKORY11 7.0
END DESCRIPTION:
XS GIS Cut Line= 3
      2738839.96     10214807.89      2738712.50     10215749.00
      2739308.45     10216417.14
#Sta/Elev= 30
  4050.3 1235.35  4134.1 1234.48  4198.1 1233.29  4307.8 1231.83  4348.2 1229.77
  4398.7 1229.54  4424.3 1227.70  4580.3 1221.56  4748.8 1219.71  4847.4 1219.42
  4953.7 1219.42  4973.9 1215.75  4984.0 1216.55  4997.6 1215.39  4997.8 1214.89
  5001.6 1215.39  5069.1 1218.99  5111.7 1217.59  5139.5 1219.95  5175.3 1219.43
  5182.0 1220.66  5217.9 1222.10  5316.6 1223.07  5338.3 1222.18  5649.3 1230.69
  5783.9 1232.31  5805.7 1231.45  5826.6 1233.04  5834.1 1232.00  5895.3 1232.32
#Mann=8,-1,0
  4050.3    0.12       0  4134.1    0.05       0  4198.1    0.12       0
  4424.3    0.05       0  4748.8    0.12       0  4847.4    0.05       0
  4997.6    0.03       0  5001.6    0.05       0
Bank Sta=4997.6,5001.6
Exp/Cntr=0.3,0.1

Type RM Length L Ch R = 1,2476,446,446,446
BEGIN DESCRIPTION:
Mapping XS 77206b99
END DESCRIPTION:
XS GIS Cut Line= 4
      2737854.01     10215422.66      2738005.06     10215683.09
      2738265.48     10215922.67      2738416.54     10216115.40
#Sta/Elev= 30
  4670.9 1217.32  4702.2 1217.09  4717.7 1217.89  4723.7 1217.12  4739.5 1217.56
  4775.5 1216.76  4958.9 1215.93  4969.1 1215.10  4979.5 1214.91  4986.4 1212.11
  5012.6 1210.98  5012.9 1210.48  5016.4 1210.48  5016.6 1210.98  5028.8 1213.90
  5036.2 1214.89  5128.1 1214.76  5149.5 1215.82  5156.4 1216.74  5184.8 1217.72
  5213.1 1219.60  5219.9 1219.28  5241.5 1220.93  5262.5 1221.32  5269.9 1222.03
  5319.2 1223.66  5322.6 1224.22  5418.5 1225.71  5482.7 1225.63  5570.7 1224.48
#Mann=3,-1,0
  4670.9    0.05       0  5012.6    0.03       0  5016.6    0.05       0
Bank Sta=5012.6,5016.6
Exp/Cntr=0.3,0.1

Type RM Length L Ch R = 1,2030,545,545,545
BEGIN DESCRIPTION:
Mapping XS def2ffc6
END DESCRIPTION:
XS GIS Cut Line= 3
      2737791.53     10215849.78      2737911.31     10216089.34
      2738265.50     10216365.40
#Sta/Elev= 30
  4719.7 1215.47  4868.8 1214.95  4880.0 1214.21  4902.3 1213.82  4919.1 1212.10
  4941.4 1212.56  4958.2 1210.64  4998.6 1209.02  4998.9 1208.52  5002.4 1208.52
  5002.6 1209.02  5015.1 1210.54  5021.4 1212.46  5093.8 1216.53  5100.1 1217.26
  5114.6 1217.58  5143.5 1217.06  5149.9 1214.84  5164.4 1215.34  5170.7 1216.46
  5178.8 1216.28  5185.2 1215.43  5193.3 1216.21  5199.6 1217.62  5207.8 1218.09
  5214.1 1219.12  5243.1 1220.53  5328.1 1222.86  5406.8 1223.23  5436.6 1222.33
#Mann=3,-1,0
  4719.7    0.05       0  4998.6    0.03       0  5002.6    0.05       0
Bank Sta=4998.6,5002.6
Exp/Cntr=0.3,0.1

Type RM Length L Ch R = 1,1485,238,238,238
BEGIN DESCRIPTION:
Mapping XS d3c8002f
END DESCRIPTION:
XS GIS Cut Line= 3
      2737463.41     10216339.36      2737577.98     10216479.97
      2737707.19     10216609.17
#Sta/Elev= 30
  4847.6 1211.81  4865.5 1211.75  4873.4 1212.60  4879.8 1212.78  4894.2 1212.43
  4902.1 1212.60  4922.9 1212.00  4937.3 1212.20  4943.7 1211.22  4951.6 1210.93
  4980.4 1207.05  4991.9 1206.71  4992.3 1206.21  4996.4 1206.21  4996.7 1206.71
  5007.6 1207.13  5022.0 1207.05  5043.7 1207.51  5057.9 1209.45  5064.9 1211.99
  5072.0 1212.31  5079.1 1213.62  5107.4 1215.37  5128.6 1216.25  5149.8 1216.53
  5171.0 1217.37  5178.1 1217.18  5185.1 1217.67  5192.2 1217.23  5211.7 1217.71
#Mann=3,-1,0
  4847.6    0.05       0  4991.9    0.03       0  4996.7    0.05       0
Bank Sta=4991.9,4996.7
Exp/Cntr=0.3,0.1

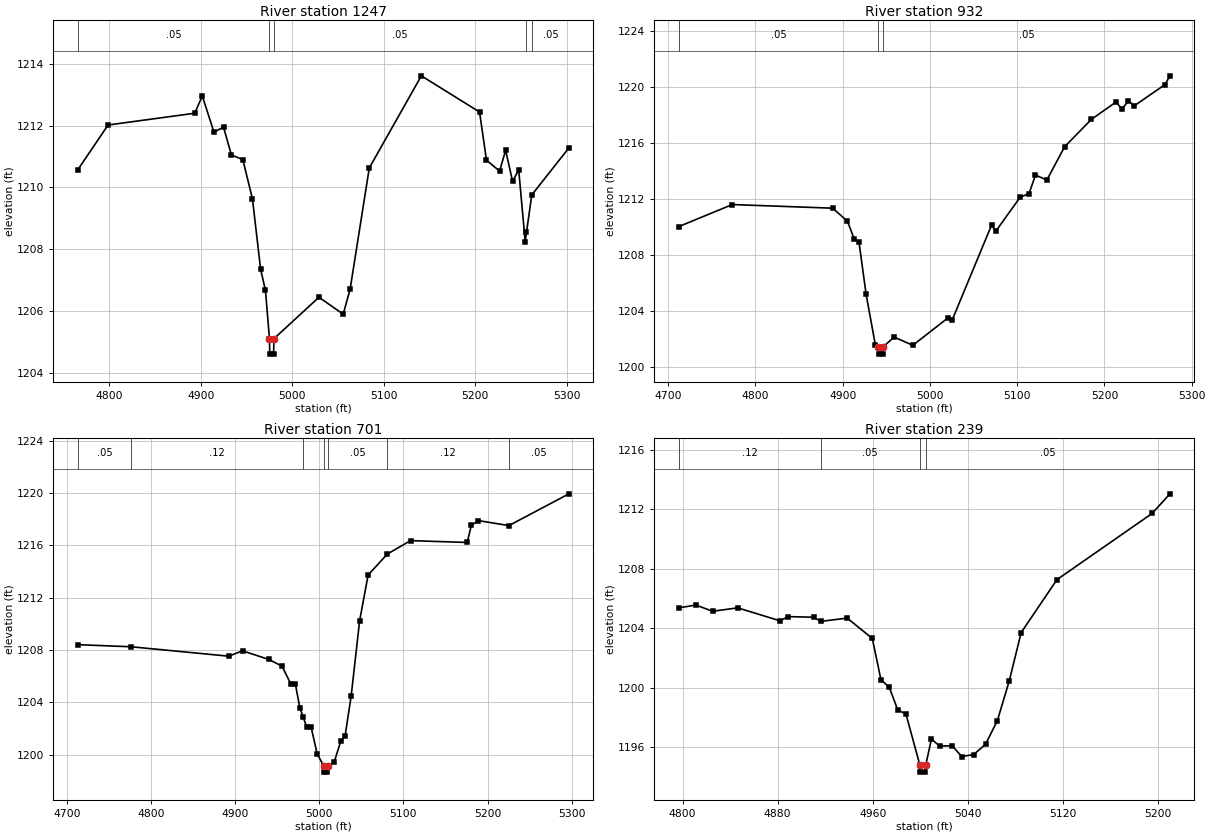
Type RM Length L Ch R = 1,1247,315,315,315
BEGIN DESCRIPTION:
Mapping XS a642186d
END DESCRIPTION:
XS GIS Cut Line= 3
      2737317.57     10216401.85      2737400.90     10216657.05
      2737577.10     10216859.17
#Sta/Elev= 30
  4765.8 1210.58  4798.7 1212.02  4893.4 1212.40  4901.7 1212.96  4914.4 1211.79
  4924.9 1211.95  4933.5 1211.05  4946.0 1210.90  4956.5 1209.63  4965.4 1207.36
  4970.7 1206.67  4975.1 1205.11  4975.4 1204.61  4979.6 1204.61  4980.0 1205.11
  5029.2 1206.45  5055.7 1205.90  5063.3 1206.72  5084.2 1210.63  5141.1 1213.61
  5204.7 1212.44  5212.3 1210.88  5226.6 1210.53  5233.2 1211.20  5240.8 1210.20
  5247.5 1210.57  5254.6 1208.25  5256.0 1208.55  5261.8 1209.76  5302.4 1211.28
#Mann=5,-1,0
  4765.8    0.05       0  4975.1    0.03       0  4980.0    0.05       0
  5256.0    0.12       0  5261.8    0.05       0
Bank Sta=4975.1,4980
Exp/Cntr=0.3,0.1

Type RM Length L Ch R = 1,932,231,231,231
BEGIN DESCRIPTION:
Mapping XS 0c8abd4a
END DESCRIPTION:
XS GIS Cut Line= 4
      2737203.00     10216422.63      2737104.02     10216683.09
      2737140.48     10216860.17      2737208.12     10216938.22
#Sta/Elev= 30
  4712.4 1210.02  4773.5 1211.59  4888.6 1211.33  4905.5 1210.40  4913.4 1209.10
  4918.7 1208.92  4926.9 1205.17  4937.6 1201.52  4941.0 1201.40  4941.4 1200.90
  4945.7 1200.90  4946.0 1201.40  4959.0 1202.12  4980.4 1201.53  5020.3 1203.47
  5025.4 1203.32  5070.6 1210.11  5075.7 1209.70  5103.4 1212.11  5113.6 1212.37
  5121.0 1213.70  5134.0 1213.34  5154.4 1215.72  5184.9 1217.67  5213.4 1218.92
  5220.0 1218.41  5227.6 1219.00  5234.2 1218.65  5269.4 1220.16  5275.1 1220.79
#Mann=3,-1,0
  4712.4    0.05       0  4941.0    0.03       0  4946.0    0.05       0
Bank Sta=4941,4946
Exp/Cntr=0.3,0.1

Type RM Length L Ch R = 1,701,462,462,462
BEGIN DESCRIPTION:
Mapping XS 68a5d17d
END DESCRIPTION:
XS GIS Cut Line= 3
      2736973.82     10216443.49      2736885.27     10216703.92
      2736926.73     10217009.65
#Sta/Elev= 30
  4713.2 1208.41  4776.4 1208.25  4892.4 1207.53  4908.8 1207.94  4940.1 1207.28
  4955.7 1206.77  4966.2 1205.41  4971.5 1205.44  4976.9 1203.59  4981.0 1202.85
  4985.2 1202.09  4990.4 1202.09  4997.5 1200.06  5005.1 1199.16  5005.5 1198.66
  5009.8 1198.66  5010.1 1199.16  5017.7 1199.42  5025.7 1201.05  5030.7 1201.42
  5037.9 1204.46  5048.0 1210.24  5058.1 1213.74  5080.9 1215.34  5108.5 1216.37
  5175.8 1216.23  5180.8 1217.54  5189.3 1217.90  5225.4 1217.52  5296.8 1219.95
#Mann=7,-1,0
  4713.2    0.05       0  4776.4    0.12       0  4981.0    0.05       0
  5005.1    0.05       0  5010.1    0.05       0  5080.9    0.12       0
  5225.4    0.05       0
Bank Sta=5005.1,5010.1
Exp/Cntr=0.3,0.1

Type RM Length L Ch R = 1,239,0,0,0
BEGIN DESCRIPTION:
HICKORY11 6.0
END DESCRIPTION:
XS GIS Cut Line= 3
      2736580.70     10216528.10      2736424.08     10216692.04
      2736430.68     10216878.10
#Sta/Elev= 30
  4797.0 1205.38  4811.2 1205.57  4825.3 1205.15  4846.4 1205.38  4881.9 1204.51
  4888.9 1204.79  4910.2 1204.75  4916.3 1204.47  4938.5 1204.69  4959.6 1203.32
  4966.9 1200.53  4973.8 1200.05  4981.0 1198.51  4987.9 1198.24  4999.5 1194.83
  4999.9 1194.33  5004.2 1194.33  5004.6 1194.83  5009.3 1196.55  5016.2 1196.09
  5026.8 1196.10  5034.8 1195.38  5044.8 1195.51  5054.8 1196.20  5064.8 1197.80
  5074.8 1200.48  5084.8 1203.72  5114.9 1207.28  5194.9 1211.73  5209.9 1213.05
#Mann=4,-1,0
  4797.0    0.12       0  4916.3    0.05       0  4999.5    0.05       0
  5004.6    0.05       0
Bank Sta=4999.5,5004.6
Exp/Cntr=0.3,0.1

Chan Stop Cuts=-1