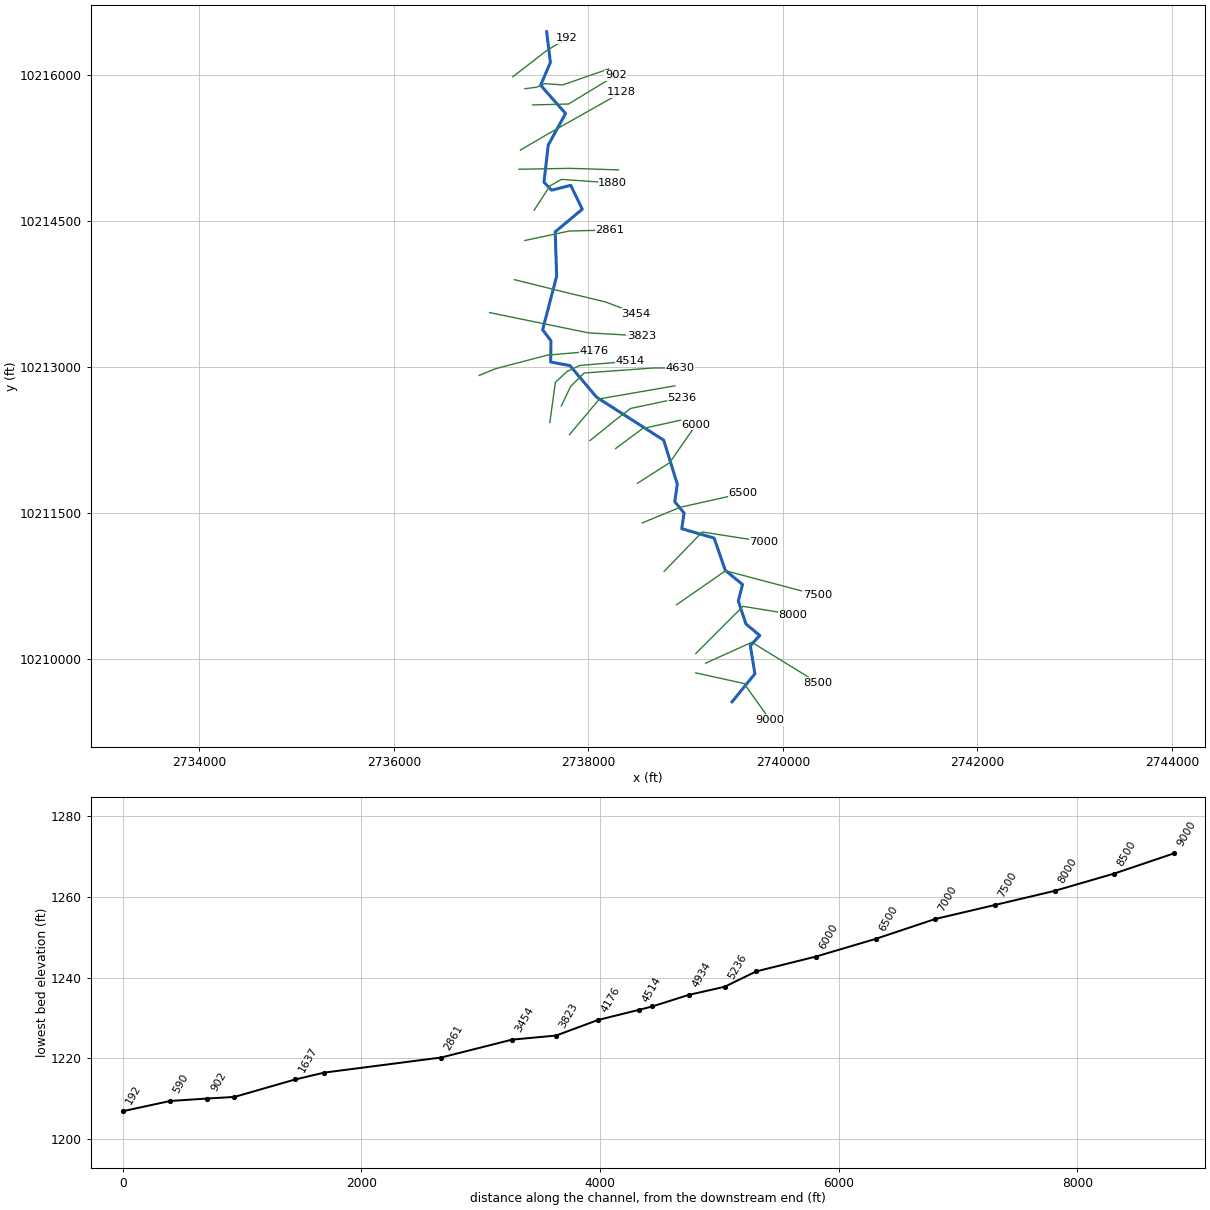
--- HICKORY12.prj (project) ---

Proj Title=HICKORY12 Base Level Engineering
Current Plan=p01
Default Exp/Contr=0.3,0.1
English Units
Geom File=g01
Flow File=f01
Plan File=p01
BEGIN DESCRIPTION:
HICKORY12
END DESCRIPTION:

--- HICKORY12.p01 (plan) ---

Plan Title=Multiple Run
Short Identifier=Multiple
Geom File=g01
Flow File=f01
Subcritical Flow
K Sum by GR= 0
Std Step Tol= 0.01
Critical Tol= 0.01
Num of Std Step Trials= 20
Max Error Tol= 0.3
Flow Tol Ratio= 0.001
Split Flow NTrial= 30
Split Flow Tol= 0.02
Split Flow Ratio= 0.02
Log Output Level= 0
Friction Slope Method= 1
Unsteady Friction Slope Method= 2
Unsteady Bridges Friction Slope Method= 1
Parabolic Critical Depth
Global Vel Dist=  1 , 1 , 1
Global Log Level= 0
CheckData=True
Encroach Param= -1, 0, 0, 0
BEGIN DESCRIPTION:
Multiple Run
END DESCRIPTION:

--- HICKORY12.f01 (steady flow) ---

Flow Title=Multiple
Number of Profiles=7
Profile Names=10-year,25-year,50-year,1pct_min,100-year,1pct_plu,500-year
River Rch & RM= HICKORY12,Reach-1,9000
     382     619     681     410     775    1466    1038
River Rch & RM= HICKORY12,Reach-1,192
     503     817     893     659    1159    2036    1533
Boundary for River Rch & Prof#=HICKORY12,Reach-1,1
Up Type=0
Dn Type=3
Dn Slope=0.005
Boundary for River Rch & Prof#=HICKORY12,Reach-1,2
Up Type=0
Dn Type=3
Dn Slope=0.005
Boundary for River Rch & Prof#=HICKORY12,Reach-1,3
Up Type=0
Dn Type=3
Dn Slope=0.005
Boundary for River Rch & Prof#=HICKORY12,Reach-1,4
Up Type=0
Dn Type=3
Dn Slope=0.005
Boundary for River Rch & Prof#=HICKORY12,Reach-1,5
Up Type=0
Dn Type=3
Dn Slope=0.005
Boundary for River Rch & Prof#=HICKORY12,Reach-1,6
Up Type=0
Dn Type=3
Dn Slope=0.005
Boundary for River Rch & Prof#=HICKORY12,Reach-1,7
Up Type=0
Dn Type=3
Dn Slope=0.005

--- HICKORY12.g01 (geometry) ---

Geom Title=Existing Conditions

River Reach=HICKORY12,Reach-1
Reach XY= 30
      2739477.25     10209555.00      2739712.50     10209844.00
      2739665.50     10210133.00      2739762.25     10210238.00
      2739620.75     10210356.00      2739541.75     10210593.00
      2739585.50     10210762.00      2739407.75     10210908.00
      2739293.50     10211239.00      2738960.25     10211336.00
      2738984.25     10211497.00      2738888.50     10211614.00
      2738914.50     10211794.00      2738774.75     10212246.00
      2738084.50     10212688.00      2737810.75     10213013.00
      2737612.25     10213050.00      2737615.50     10213268.00
      2737530.00     10213381.00      2737673.75     10213932.00
      2737659.25     10214389.00      2737937.50     10214621.00
      2737818.75     10214867.00      2737622.00     10214817.00
      2737543.75     10214899.00      2737587.50     10215280.00
      2737765.50     10215605.00      2737509.25     10215896.00
      2737609.50     10216130.00      2737571.25     10216446.00

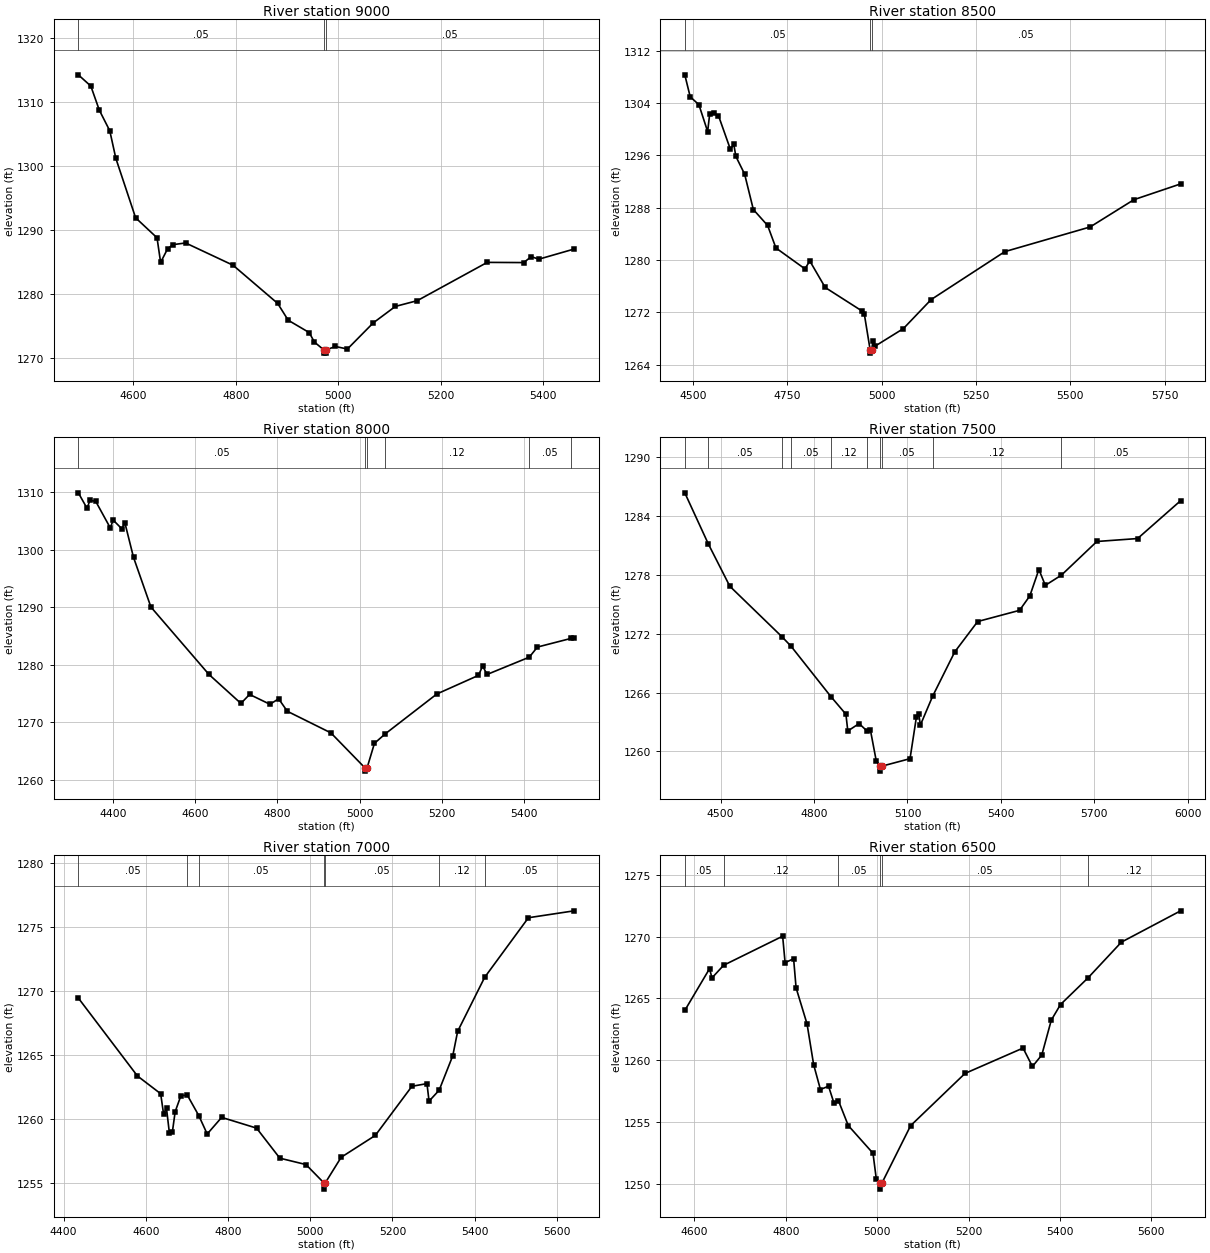
Type RM Length L Ch R = 1,9000,500,500,500
BEGIN DESCRIPTION:
HICKORY12 18.0
END DESCRIPTION:
XS GIS Cut Line= 3
      2739105.70     10209853.11      2739601.09     10209743.83
      2739868.65     10209369.04
#Sta/Elev= 30
  4492.7 1314.31  4517.1 1312.55  4533.6 1308.79  4554.1 1305.55  4565.9 1301.24
  4604.5 1291.94  4646.3 1288.81  4653.3 1284.96  4666.8 1287.06  4677.0 1287.73
  4702.1 1288.00  4794.6 1284.52  4881.8 1278.54  4902.3 1275.91  4943.3 1273.98
  4953.5 1272.49  4972.0 1271.26  4972.2 1270.76  4975.7 1270.76  4976.0 1271.26
  4994.5 1271.80  5017.9 1271.40  5068.3 1275.49  5111.5 1278.07  5154.3 1278.97
  5290.8 1284.96  5362.0 1284.93  5376.8 1285.86  5391.5 1285.46  5460.5 1287.05
#Mann=3,-1,0
  4492.7    0.05       0  4972.0    0.05       0  4976.0    0.05       0
Bank Sta=4972,4976
Exp/Cntr=0.3,0.1

Type RM Length L Ch R = 1,8500,500,500,500
BEGIN DESCRIPTION:
HICKORY12 17.0
END DESCRIPTION:
XS GIS Cut Line= 3
      2739205.72     10209953.13      2739680.95     10210167.87
      2740355.67     10209753.12
#Sta/Elev= 30
  4478.5 1308.30  4492.8 1304.95  4515.9 1303.73  4539.0 1299.63  4544.5 1302.35
  4555.3 1302.43  4567.6 1302.08  4599.2 1296.93  4608.3 1297.66  4613.8 1295.83
  4636.9 1293.14  4660.1 1287.71  4697.9 1285.28  4719.9 1281.84  4796.7 1278.65
  4809.7 1279.85  4850.5 1275.80  4948.4 1272.19  4953.9 1271.80  4969.5 1266.27
  4969.8 1265.77  4973.5 1266.27  4977.0 1267.61  4983.2 1266.86  5057.6 1269.52
  5131.0 1273.95  5326.3 1281.28  5552.3 1285.05  5668.3 1289.22  5792.0 1291.63
#Mann=3,-1,0
  4478.5    0.05       0  4969.5    0.05       0  4973.5    0.05       0
Bank Sta=4969.5,4973.5
Exp/Cntr=0.3,0.1

Type RM Length L Ch R = 1,8000,500,500,500
BEGIN DESCRIPTION:
HICKORY12 16.0
END DESCRIPTION:
XS GIS Cut Line= 3
      2739105.67     10210053.09      2739589.82     10210537.68
      2740105.73     10210453.10
#Sta/Elev= 30
  4315.0 1309.93  4336.2 1307.24  4343.3 1308.63  4357.4 1308.44  4392.8 1303.83
  4399.9 1305.18  4421.1 1303.66  4428.2 1304.76  4449.4 1298.70  4491.8 1290.05
  4633.2 1278.31  4711.0 1273.27  4732.2 1274.83  4781.7 1273.12  4802.9 1274.07
  4824.1 1271.90  4930.2 1268.14  5014.1 1261.98  5014.3 1261.48  5018.1 1261.98
  5036.3 1266.32  5062.3 1267.95  5188.3 1274.91  5289.7 1278.15  5299.8 1279.77
  5310.7 1278.31  5413.5 1281.32  5433.3 1283.08  5514.3 1284.57  5522.8 1284.71
#Mann=6,-1,0
  4315.0    0.05       0  5014.1    0.03       0  5018.1    0.05       0
  5062.3    0.12       0  5413.5    0.05       0  5514.3    0.12       0
Bank Sta=5014.1,5018.1
Exp/Cntr=0.3,0.1

Type RM Length L Ch R = 1,7500,500,500,500
BEGIN DESCRIPTION:
HICKORY12 15.0
END DESCRIPTION:
XS GIS Cut Line= 3
      2738905.69     10210553.12      2739411.03     10210903.63
      2740355.67     10210653.11
#Sta/Elev= 30
  4385.0 1286.36  4460.7 1281.14  4529.5 1276.84  4697.0 1271.69  4726.3 1270.72
  4854.4 1265.58  4902.4 1263.79  4908.5 1262.08  4944.8 1262.84  4971.1 1262.05
  4981.3 1262.14  4999.8 1259.04  5013.2 1258.49  5013.4 1257.99  5017.2 1258.49
  5108.3 1259.26  5129.0 1263.55  5136.4 1263.80  5141.5 1262.68  5181.1 1265.64
  5251.8 1270.14  5325.5 1273.24  5460.0 1274.38  5493.0 1275.85  5522.1 1278.54
  5542.8 1276.93  5594.5 1277.97  5708.3 1281.40  5839.2 1281.70  5977.3 1285.56
#Mann=10,-1,0
  4385.0    0.12       0  4460.7    0.05       0  4697.0    0.12       0
  4726.3    0.05       0  4854.4    0.12       0  4971.1    0.05       0
  5013.2    0.03       0  5017.2    0.05       0  5181.1    0.12       0
  5594.5    0.05       0
Bank Sta=5013.2,5017.2
Exp/Cntr=0.3,0.1

Type RM Length L Ch R = 1,7000,500,500,500
BEGIN DESCRIPTION:
HICKORY12 14.0
END DESCRIPTION:
XS GIS Cut Line= 3
      2738778.85     10210896.80      2739171.24     10211302.06
      2739805.67     10211203.11
#Sta/Elev= 30
  4435.9 1269.46  4579.6 1263.37  4636.2 1261.98  4643.2 1260.41  4650.4 1260.83
  4657.3 1258.94  4664.5 1258.95  4671.5 1260.58  4685.6 1261.84  4701.2 1261.86
  4728.9 1260.27  4749.4 1258.83  4784.6 1260.13  4869.5 1259.29  4926.1 1256.94
  4989.7 1256.44  5032.9 1255.02  5033.1 1254.52  5036.9 1255.02  5075.3 1257.01
  5158.4 1258.72  5247.4 1262.56  5284.0 1262.77  5289.1 1261.40  5313.6 1262.25
  5346.8 1264.95  5358.7 1266.86  5424.4 1271.08  5530.8 1275.74  5642.1 1276.28
#Mann=7,-1,0
  4435.9    0.05       0  4701.2    0.12       0  4728.9    0.05       0
  5032.9    0.05       0  5036.9    0.05       0  5313.6    0.12       0
  5424.4    0.05       0
Bank Sta=5032.9,5036.9
Exp/Cntr=0.3,0.1

Type RM Length L Ch R = 1,6500,500,500,500
BEGIN DESCRIPTION:
HICKORY12 13.0
END DESCRIPTION:
XS GIS Cut Line= 3
      2738554.79     10211395.88      2738944.31     10211555.87
      2739592.13     10211701.08
#Sta/Elev= 30
  4578.9 1264.03  4633.0 1267.40  4638.4 1266.66  4663.8 1267.68  4793.0 1270.03
  4798.4 1267.89  4817.0 1268.21  4822.4 1265.86  4846.4 1262.94  4860.9 1259.64
  4875.7 1257.64  4893.4 1257.91  4905.1 1256.57  4915.1 1256.74  4936.6 1254.73
  4990.7 1252.49  4998.0 1250.40  5006.4 1250.09  5006.6 1249.59  5010.4 1250.09
  5073.1 1254.72  5192.1 1258.94  5319.1 1260.99  5339.6 1259.50  5360.1 1260.43
  5380.9 1263.25  5401.1 1264.51  5461.2 1266.66  5534.3 1269.55  5663.9 1272.08
#Mann=6,-1,0
  4578.9    0.05       0  4663.8    0.12       0  4915.1    0.05       0
  5006.4    0.05       0  5010.4    0.05       0  5461.2    0.12       0
Bank Sta=5006.4,5010.4
Exp/Cntr=0.3,0.1

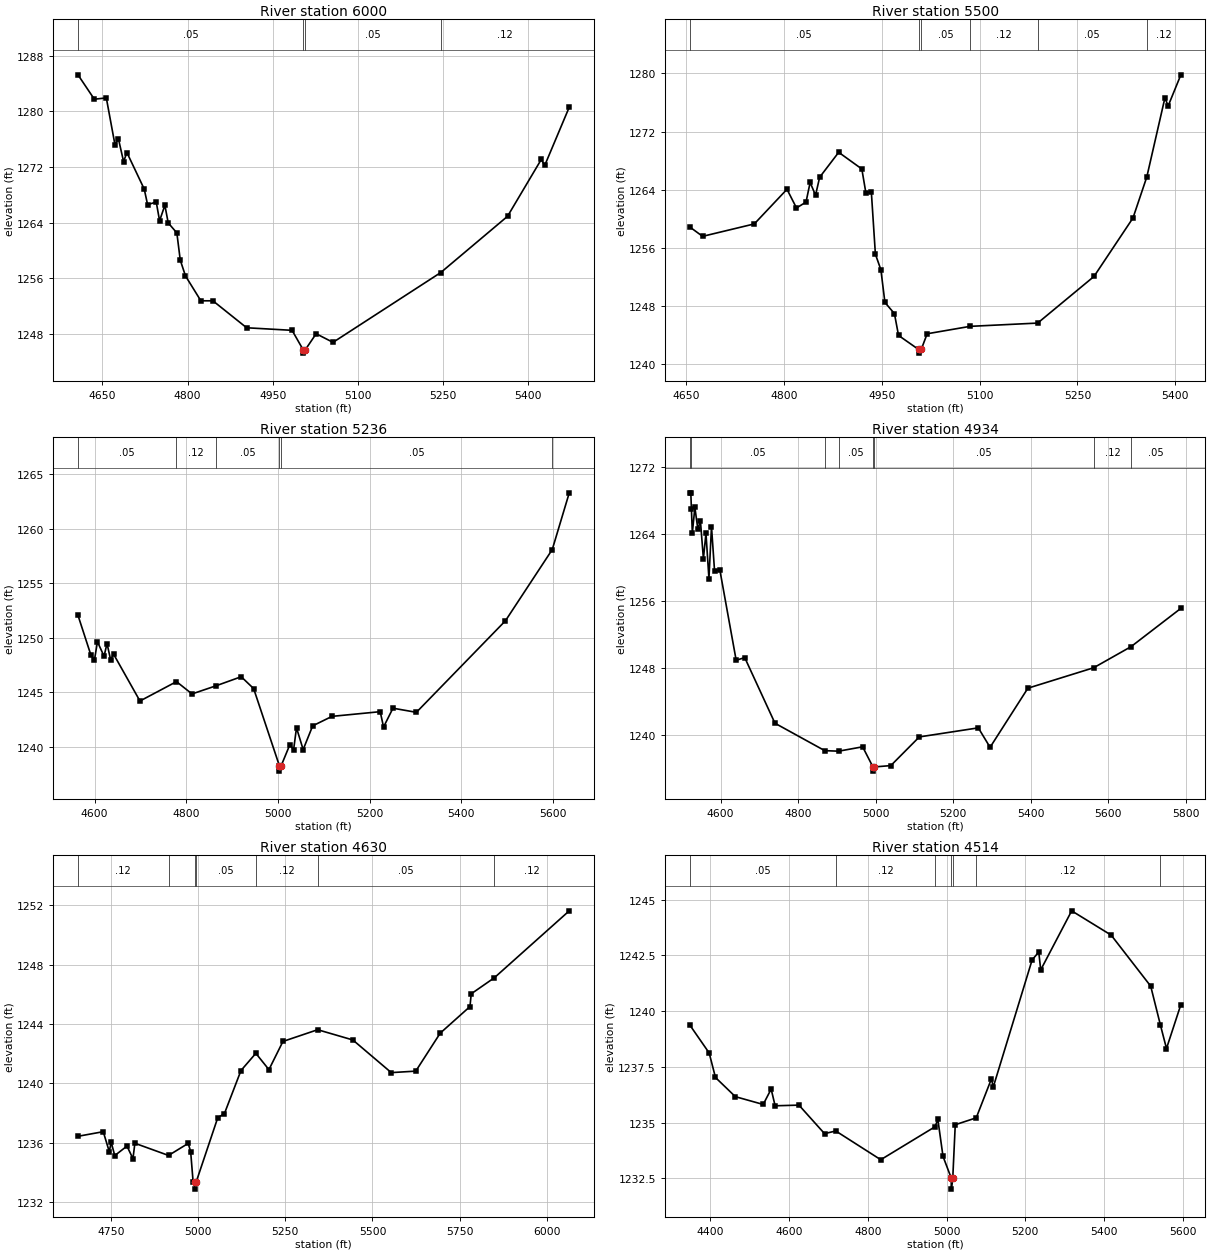
Type RM Length L Ch R = 1,6000,500,500,500
BEGIN DESCRIPTION:
HICKORY12 12.0
END DESCRIPTION:
XS GIS Cut Line= 3
      2738505.67     10211803.11      2738836.61     10212015.27
      2739105.66     10212403.07
#Sta/Elev= 30
  4606.9 1285.27  4635.7 1281.76  4656.8 1281.95  4672.0 1275.22  4678.2 1276.03
  4687.2 1272.79  4693.1 1274.08  4723.6 1268.82  4729.5 1266.58  4744.7 1266.97
  4750.6 1264.27  4759.9 1266.50  4765.8 1263.96  4781.0 1262.52  4787.0 1258.61
  4796.2 1256.33  4823.3 1252.75  4844.5 1252.75  4903.9 1248.87  4983.9 1248.50
  5003.3 1245.72  5003.6 1245.22  5007.3 1245.72  5026.3 1248.01  5056.0 1246.77
  5245.8 1256.82  5363.3 1264.91  5422.7 1273.09  5428.8 1272.23  5472.0 1280.62
#Mann=4,-1,0
  4606.9    0.05       0  5003.3    0.05       0  5007.3    0.05       0
  5245.8    0.12       0
Bank Sta=5003.3,5007.3
Exp/Cntr=0.3,0.1

Type RM Length L Ch R = 1,5500,264,264,264
BEGIN DESCRIPTION:
HICKORY12 11.0
END DESCRIPTION:
XS GIS Cut Line= 3
      2738279.77     10212159.75      2738556.57     10212365.35
      2738955.73     10212453.12
#Sta/Elev= 30
  4655.2 1258.91  4675.2 1257.60  4754.5 1259.31  4804.6 1264.07  4819.2 1261.50
  4833.8 1262.31  4840.1 1265.01  4848.4 1263.25  4854.7 1265.72  4883.9 1269.15
  4919.4 1266.86  4925.6 1263.58  4934.0 1263.69  4940.2 1255.15  4948.6 1253.02
  4954.8 1248.52  4969.4 1246.98  4975.7 1243.98  5006.5 1242.05  5006.8 1241.55
  5010.5 1242.05  5019.6 1244.21  5085.4 1245.23  5189.1 1245.68  5275.5 1252.09
  5335.3 1260.13  5356.5 1265.77  5384.2 1276.61  5389.3 1275.54  5408.7 1279.80
#Mann=6,-1,0
  4655.2    0.05       0  5006.5    0.05       0  5010.5    0.05       0
  5085.4    0.12       0  5189.1    0.05       0  5356.5    0.12       0
Bank Sta=5006.5,5010.5
Exp/Cntr=0.3,0.1

Type RM Length L Ch R = 1,5236,302,302,302
BEGIN DESCRIPTION:
Mapping XS 5b3f0f0d
END DESCRIPTION:
XS GIS Cut Line= 4
      2738016.81     10212242.11      2738285.88     10212459.10
      2738433.45     10212571.94      2738961.85     10212684.55
#Sta/Elev= 30
  4563.6 1252.06  4591.7 1248.42  4599.6 1247.98  4606.1 1249.63  4620.5 1248.30
  4626.9 1249.47  4634.8 1247.99  4641.3 1248.49  4698.8 1244.19  4778.5 1245.97
  4812.4 1244.84  4864.3 1245.58  4919.7 1246.42  4946.8 1245.33  5002.9 1238.25
  5003.2 1237.75  5006.9 1238.25  5025.7 1240.17  5034.0 1239.73  5040.3 1241.73
  5054.8 1239.73  5075.6 1241.91  5117.8 1242.78  5222.9 1243.21  5230.2 1241.80
  5250.7 1243.53  5301.8 1243.15  5496.1 1251.56  5598.2 1258.10  5635.3 1263.31
#Mann=6,-1,0
  4563.6    0.05       0  4778.5    0.12       0  4864.3    0.05       0
  5002.9    0.05       0  5006.9    0.05       0  5598.2    0.12       0
Bank Sta=5002.9,5006.9
Exp/Cntr=0.3,0.1

Type RM Length L Ch R = 1,4934,304,304,304
BEGIN DESCRIPTION:
HICKORY12 10.0
END DESCRIPTION:
XS GIS Cut Line= 3
      2737805.70     10212303.13      2738114.50     10212671.00
      2738891.00     10212805.15
#Sta/Elev= 30
  4519.7 1268.92  4522.9 1268.92  4524.5 1266.95  4526.8 1264.12  4533.4 1267.18
  4541.1 1264.57  4547.7 1265.59  4555.4 1261.05  4562.0 1264.10  4569.7 1258.69
  4576.3 1264.89  4584.1 1259.65  4598.0 1259.68  4640.0 1248.95  4662.1 1249.27
  4740.2 1241.44  4868.8 1238.17  4904.6 1238.11  4966.5 1238.63  4993.1 1236.23
  4993.4 1235.73  4997.1 1236.23  5039.2 1236.39  5112.8 1239.81  5265.1 1240.89
  5295.5 1238.57  5393.1 1245.62  5563.0 1248.06  5659.6 1250.58  5788.0 1255.14
#Mann=8,-1,0
  4519.7    0.12       0  4524.5    0.05       0  4868.8    0.12       0
  4904.6    0.05       0  4993.1    0.05       0  4997.1    0.05       0
  5563.0    0.12       0  5659.6    0.05       0
Bank Sta=4993.1,4997.1
Exp/Cntr=0.3,0.1

Type RM Length L Ch R = 1,4630,116,116,116
BEGIN DESCRIPTION:
Mapping XS 0f2bd6b3
END DESCRIPTION:
XS GIS Cut Line= 5
      2737721.64     10212597.98      2737817.13     10212797.64
      2737956.02     10212936.53      2738667.82     10212988.61
      2738945.58     10212988.61
#Sta/Elev= 30
  4655.3 1236.44  4727.8 1236.75  4745.0 1235.41  4750.5 1236.04  4760.8 1235.14
  4795.8 1235.78  4813.0 1234.93  4818.5 1235.97  4915.0 1235.15  4971.4 1235.96
  4978.5 1235.41  4985.5 1233.38  4990.6 1233.38  4990.9 1232.88  4994.6 1233.38
  5056.2 1237.69  5075.4 1237.97  5122.8 1240.87  5165.5 1242.03  5203.0 1240.93
  5243.2 1242.83  5342.8 1243.62  5443.7 1242.93  5554.0 1240.73  5624.2 1240.83
  5694.4 1243.39  5779.7 1245.18  5783.3 1246.04  5849.6 1247.12  6064.5 1251.63
#Mann=7,-1,0
  4655.3    0.12       0  4915.0    0.05       0  4990.6    0.03       0
  4994.6    0.05       0  5165.5    0.12       0  5342.8    0.05       0
  5849.6    0.12       0
Bank Sta=4990.6,4994.6
Exp/Cntr=0.3,0.1

Type RM Length L Ch R = 1,4514,338,338,338
BEGIN DESCRIPTION:
Mapping XS 077c6e14
END DESCRIPTION:
XS GIS Cut Line= 5
      2737604.02     10212427.89      2737660.88     10212841.04
      2737782.41     10212953.89      2737912.62     10213014.65
      2738432.04     10213057.94
#Sta/Elev= 30
  4347.2 1239.39  4397.0 1238.12  4413.0 1237.02  4463.5 1236.16  4534.2 1235.81
  4554.4 1236.50  4564.5 1235.75  4625.0 1235.78  4690.0 1234.50  4718.5 1234.62
  4832.8 1233.33  4970.7 1234.81  4977.8 1235.14  4990.9 1233.48  5011.7 1232.51
  5012.0 1232.01  5015.7 1232.51  5022.0 1234.90  5075.3 1235.21  5113.7 1236.95
  5118.7 1236.60  5217.3 1242.30  5234.1 1242.65  5239.1 1241.85  5317.7 1244.50
  5418.0 1243.41  5518.4 1241.12  5543.3 1239.36  5558.5 1238.32  5595.0 1240.29
#Mann=7,-1,0
  4347.2    0.05       0  4718.5    0.12       0  4970.7    0.05       0
  5011.7    0.03       0  5015.7    0.05       0  5075.3    0.12       0
  5543.3    0.05       0
Bank Sta=5011.7,5015.7
Exp/Cntr=0.3,0.1

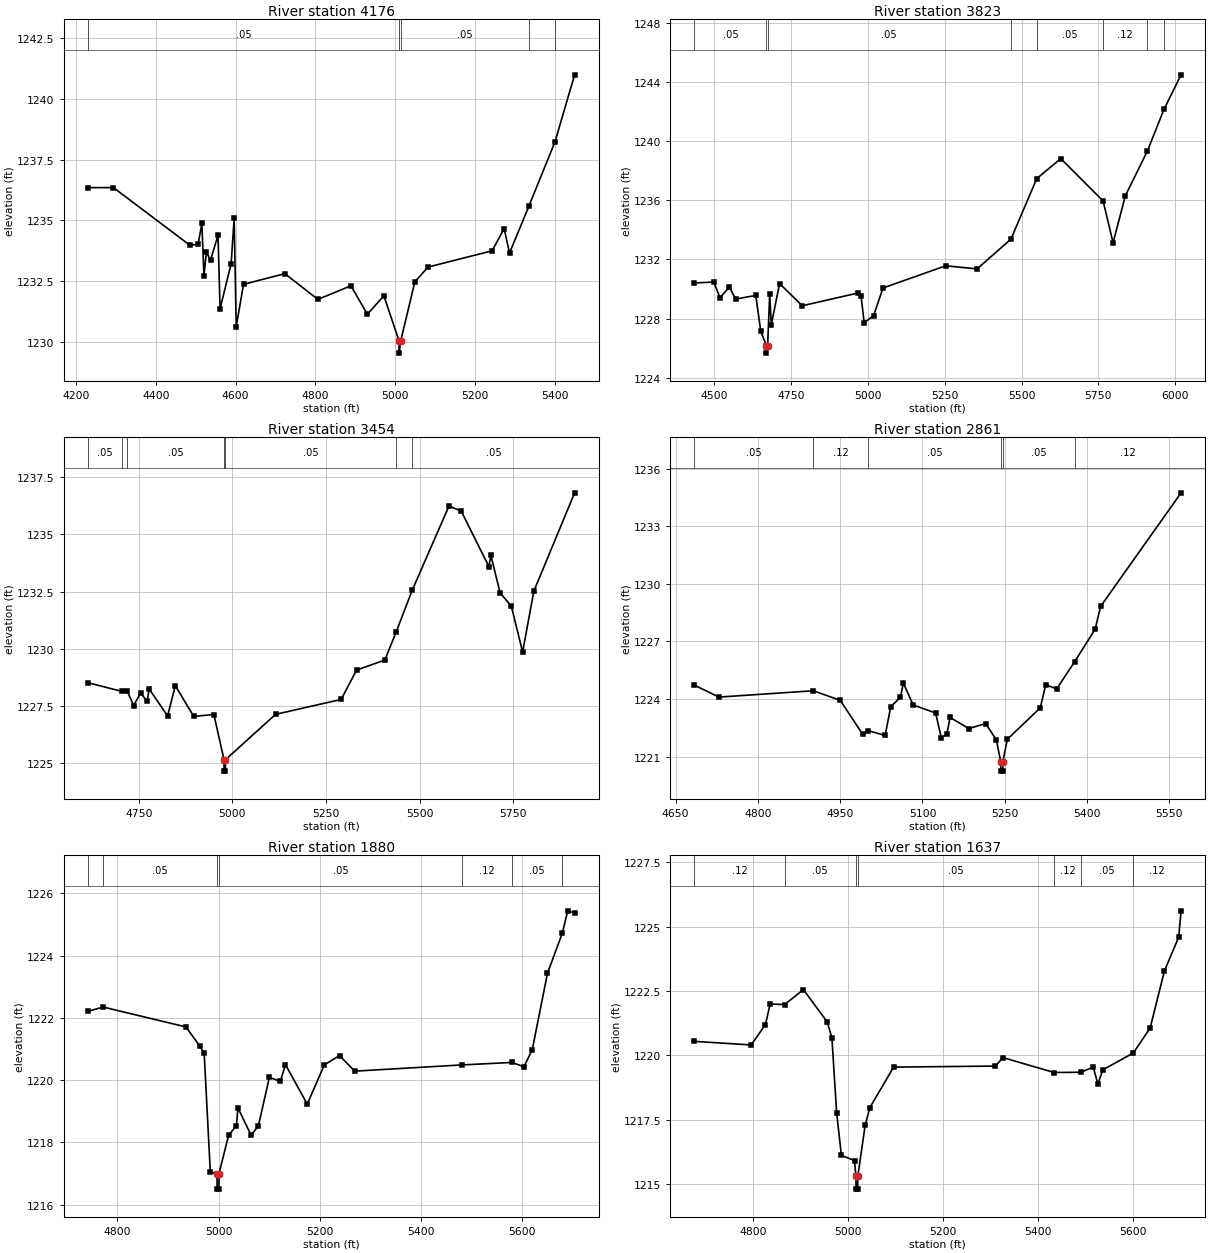
Type RM Length L Ch R = 1,4176,353,353,353
BEGIN DESCRIPTION:
Mapping XS c5a39626
END DESCRIPTION:
XS GIS Cut Line= 4
      2736876.90     10212911.37      2737041.52     10212979.97
      2737577.98     10213120.59      2738061.57     10213162.19
#Sta/Elev= 30
  4230.5 1236.35  4294.2 1236.35  4485.5 1233.98  4506.2 1234.02  4515.6 1234.88
  4520.8 1232.73  4526.9 1233.70  4537.2 1233.36  4556.0 1234.39  4561.2 1231.37
  4588.9 1233.22  4596.4 1235.08  4601.6 1230.63  4619.9 1232.37  4723.3 1232.81
  4806.0 1231.75  4888.7 1232.31  4930.0 1231.14  4971.2 1231.90  5009.3 1230.04
  5009.6 1229.54  5013.3 1230.04  5048.8 1232.47  5081.6 1233.08  5242.2 1233.75
  5272.3 1234.66  5285.9 1233.66  5334.1 1235.58  5399.6 1238.23  5448.8 1240.99
#Mann=5,-1,0
  4230.5    0.05       0  5009.3    0.03       0  5013.3    0.05       0
  5334.1    0.12       0  5399.6    0.05       0
Bank Sta=5009.3,5013.3
Exp/Cntr=0.3,0.1

Type RM Length L Ch R = 1,3823,369,369,369
BEGIN DESCRIPTION:
Mapping XS a6686099
END DESCRIPTION:
XS GIS Cut Line= 3
      2736984.27     10213558.08      2737999.86     10213349.76
      2738546.73     10213318.51
#Sta/Elev= 30
  4434.8 1230.41  4497.5 1230.47  4517.9 1229.42  4548.5 1230.13  4569.0 1229.32
  4634.5 1229.57  4650.6 1227.16  4669.0 1226.17  4669.3 1225.67  4673.0 1226.17
  4679.8 1229.65  4684.9 1227.58  4711.9 1230.37  4785.7 1228.87  4967.1 1229.73
  4977.1 1229.54  4987.5 1227.73  5018.1 1228.20  5048.7 1230.07  5252.9 1231.57
  5355.0 1231.36  5465.3 1233.37  5549.3 1237.46  5627.6 1238.81  5765.3 1235.95
  5797.9 1233.13  5838.0 1236.31  5909.3 1239.31  5963.6 1242.14  6019.3 1244.47
#Mann=8,-1,0
  4434.8    0.05       0  4669.0    0.03       0  4673.0    0.05       0
  5465.3    0.12       0  5549.3    0.05       0  5765.3    0.12       0
  5909.3    0.05       0  5963.6    0.12       0
Bank Sta=4669,4673
Exp/Cntr=0.3,0.1

Type RM Length L Ch R = 1,3454,593,593,593
BEGIN DESCRIPTION:
Mapping XS ca3d0550
END DESCRIPTION:
XS GIS Cut Line= 4
      2737239.45     10213896.63      2737786.31     10213761.22
      2738176.94     10213667.47      2738488.90     10213547.88
#Sta/Elev= 30
  4614.4 1228.52  4705.1 1228.14  4719.3 1228.15  4736.2 1227.52  4754.8 1228.07
  4772.4 1227.70  4777.6 1228.25  4826.9 1227.07  4847.5 1228.39  4896.6 1227.05
  4950.5 1227.13  4977.5 1225.16  4977.7 1224.66  4981.2 1224.66  4981.5 1225.16
  5115.3 1227.14  5290.3 1227.79  5331.4 1229.07  5406.9 1229.51  5437.5 1230.75
  5479.8 1232.55  5578.1 1236.23  5610.6 1236.02  5684.7 1233.59  5690.0 1234.08
  5714.7 1232.44  5744.7 1231.86  5774.8 1229.86  5804.8 1232.52  5913.6 1236.81
#Mann=7,-1,0
  4614.4    0.05       0  4705.1    0.12       0  4719.3    0.05       0
  4977.5    0.05       0  4981.5    0.05       0  5437.5    0.12       0
  5479.8    0.05       0
Bank Sta=4977.5,4981.5
Exp/Cntr=0.3,0.1

Type RM Length L Ch R = 1,2861,981,981,981
BEGIN DESCRIPTION:
Mapping XS ec6938d5
END DESCRIPTION:
XS GIS Cut Line= 3
      2737345.91     10214299.03      2737801.94     10214396.63
      2738222.25     10214407.01
#Sta/Elev= 30
  4684.5 1224.72  4729.1 1224.10  4901.1 1224.43  4950.2 1223.93  4991.1 1222.16
  5001.2 1222.35  5032.0 1222.10  5042.2 1223.60  5059.9 1224.09  5065.1 1224.83
  5083.1 1223.69  5124.0 1223.27  5134.2 1221.99  5144.5 1222.16  5150.2 1223.04
  5184.6 1222.46  5215.2 1222.72  5234.6 1221.87  5242.6 1220.74  5242.9 1220.24
  5246.4 1220.24  5246.6 1220.74  5254.6 1221.90  5314.7 1223.54  5324.7 1224.74
  5344.7 1224.53  5377.2 1225.94  5414.7 1227.64  5424.7 1228.83  5571.3 1234.75
#Mann=6,-1,0
  4684.5    0.05       0  4901.1    0.12       0  5001.2    0.05       0
  5242.6    0.07       0  5246.6    0.05       0  5377.2    0.12       0
Bank Sta=5242.6,5246.6
Exp/Cntr=0.3,0.1

Type RM Length L Ch R = 1,1880,243,243,243
BEGIN DESCRIPTION:
Mapping XS 26163e25
END DESCRIPTION:
XS GIS Cut Line= 4
      2737442.57     10214610.18      2737604.02     10214860.17
      2737723.81     10214927.88      2738249.22     10214890.98
#Sta/Elev= 30
  4742.0 1222.21  4771.8 1222.35  4935.6 1221.71  4962.7 1221.10  4971.7 1220.86
  4983.8 1217.04  4997.0 1217.00  4997.3 1216.50  5000.8 1216.50  5001.0 1217.00
  5020.1 1218.24  5035.3 1218.53  5038.4 1219.11  5064.5 1218.23  5078.9 1218.54
  5100.5 1220.09  5122.2 1219.96  5132.3 1220.50  5175.4 1219.23  5209.1 1220.49
  5239.2 1220.79  5269.3 1220.29  5481.1 1220.49  5580.4 1220.57  5603.6 1220.43
  5620.2 1220.98  5650.2 1223.43  5679.7 1224.73  5690.3 1225.44  5703.9 1225.37
#Mann=7,-1,0
  4742.0    0.12       0  4771.8    0.05       0  4997.0    0.03       0
  5001.0    0.05       0  5481.1    0.12       0  5580.4    0.05       0
  5679.7    0.12       0
Bank Sta=4997,5001
Exp/Cntr=0.3,0.1

Type RM Length L Ch R = 1,1637,509,509,509
BEGIN DESCRIPTION:
Mapping XS cb0e2c31
END DESCRIPTION:
XS GIS Cut Line= 3
      2737286.35     10215032.05      2737814.75     10215041.48
      2738310.71     10215025.52
#Sta/Elev= 30
  4676.5 1220.54  4795.9 1220.40  4825.9 1221.19  4835.9 1221.99  4866.4 1221.97
  4905.9 1222.55  4955.9 1221.30  4965.9 1220.68  4975.9 1217.76  4985.9 1216.11
  5013.5 1215.91  5016.5 1215.30  5016.7 1214.80  5020.2 1214.80  5020.5 1215.30
  5035.9 1217.28  5045.9 1217.97  5095.9 1219.54  5310.4 1219.58  5326.0 1219.91
  5433.7 1219.33  5490.4 1219.34  5516.1 1219.54  5526.1 1218.88  5536.1 1219.43
  5600.8 1220.09  5636.1 1221.06  5666.2 1223.28  5696.2 1224.59  5701.2 1225.61
#Mann=7,-1,0
  4676.5    0.12       0  4866.4    0.05       0  5016.5    0.03       0
  5020.5    0.05       0  5433.7    0.12       0  5490.4    0.05       0
  5600.8    0.12       0
Bank Sta=5016.5,5020.5
Exp/Cntr=0.3,0.1

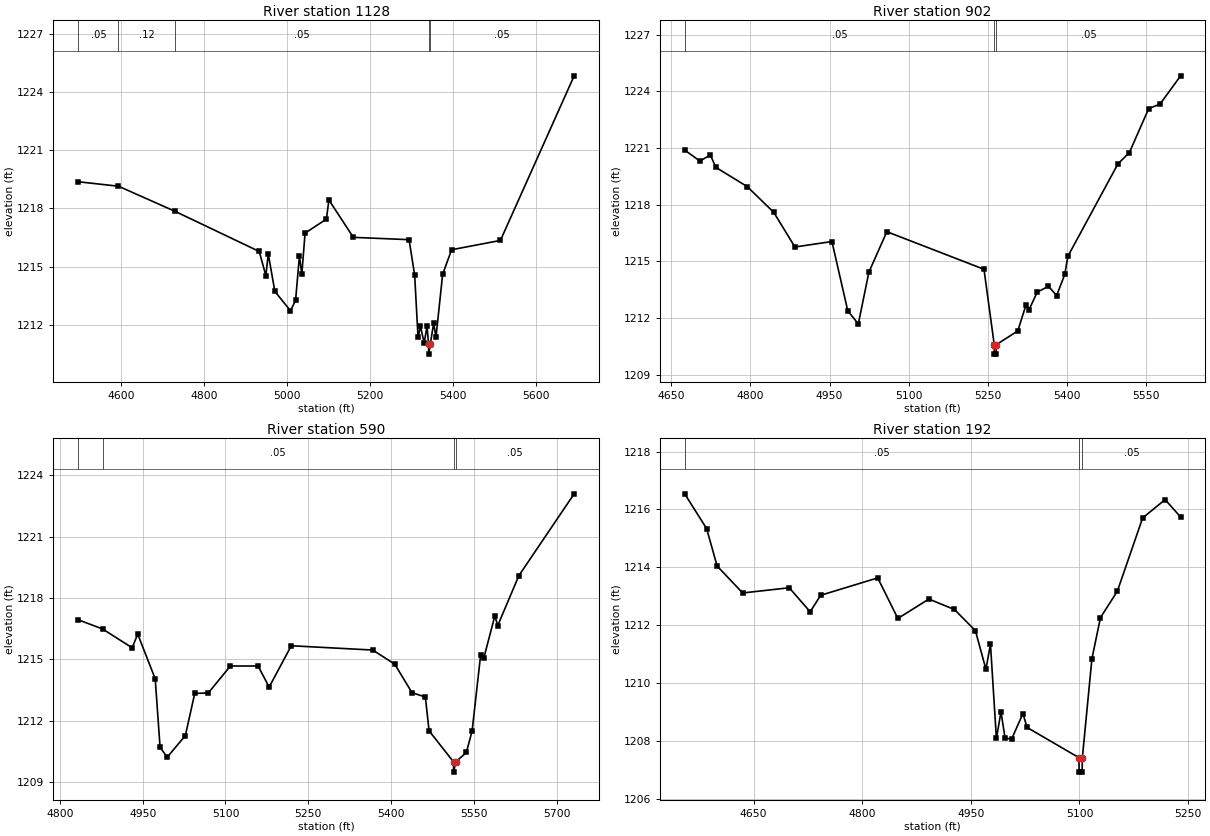
Type RM Length L Ch R = 1,1128,226,226,226
BEGIN DESCRIPTION:
Mapping XS feec293b
END DESCRIPTION:
XS GIS Cut Line= 3
      2737301.93     10215229.96      2737577.98     10215391.42
      2738340.45     10215821.89
#Sta/Elev= 30
  4496.4 1219.38  4593.5 1219.15  4730.1 1217.85  4932.8 1215.78  4948.7 1214.53
  4954.5 1215.65  4970.4 1213.72  5008.0 1212.72  5020.3 1213.25  5029.6 1215.54
  5035.4 1214.61  5043.2 1216.73  5094.6 1217.45  5100.7 1218.44  5159.5 1216.51
  5293.9 1216.39  5307.4 1214.55  5315.5 1211.34  5321.3 1211.92  5330.3 1211.05
  5337.2 1211.93  5340.9 1210.98  5341.2 1210.48  5344.9 1210.98  5353.1 1212.07
  5358.8 1211.36  5374.8 1214.60  5396.4 1215.87  5514.1 1216.35  5691.8 1224.85
#Mann=5,-1,0
  4496.4    0.05       0  4593.5    0.12       0  4730.1    0.05       0
  5340.9    0.03       0  5344.9    0.05       0
Bank Sta=5340.9,5344.9
Exp/Cntr=0.3,0.1

Type RM Length L Ch R = 1,902,312,312,312
BEGIN DESCRIPTION:
Mapping XS 19ba61a4
END DESCRIPTION:
XS GIS Cut Line= 3
      2737426.92     10215693.51      2737796.13     10215702.85
      2738283.14     10215998.97
#Sta/Elev= 30
  4675.6 1220.89  4704.4 1220.31  4724.4 1220.63  4734.4 1219.98  4794.4 1218.95
  4844.4 1217.59  4884.4 1215.76  4954.5 1216.05  4984.5 1212.38  5004.5 1211.69
  5024.5 1214.43  5058.5 1216.57  5242.5 1214.58  5261.9 1210.59  5262.1 1210.09
  5265.6 1210.09  5265.9 1210.59  5306.5 1211.32  5322.0 1212.69  5327.8 1212.44
  5343.3 1213.37  5364.6 1213.68  5380.1 1213.19  5395.5 1214.31  5401.4 1215.27
  5496.4 1220.17  5517.7 1220.75  5554.5 1223.09  5575.8 1223.32  5614.9 1224.82
#Mann=3,-1,0
  4675.6    0.05       0  5261.9    0.03       0  5265.9    0.05       0
Bank Sta=5261.9,5265.9
Exp/Cntr=0.3,0.1

Type RM Length L Ch R = 1,590,398,398,398
BEGIN DESCRIPTION:
Mapping XS fe1a7d75
END DESCRIPTION:
XS GIS Cut Line= 5
      2737348.78     10215860.17      2737468.61     10215875.80
      2737551.94     10215912.26      2737736.19     10215899.10
      2738210.18     10216064.05
#Sta/Elev= 30
  4833.3 1216.93  4877.5 1216.48  4931.0 1215.56  4941.1 1216.23  4972.8 1214.04
  4981.6 1210.69  4994.6 1210.21  5027.4 1211.27  5044.4 1213.33  5068.9 1213.35
  5109.0 1214.67  5159.1 1214.67  5179.2 1213.64  5219.3 1215.66  5366.9 1215.45
  5406.7 1214.76  5437.8 1213.37  5462.2 1213.15  5468.9 1211.50  5513.2 1209.98
  5513.4 1209.48  5517.2 1209.98  5536.4 1210.44  5546.9 1211.50  5562.2 1215.19
  5568.1 1215.06  5588.0 1217.12  5593.3 1216.65  5631.6 1219.09  5731.7 1223.09
#Mann=4,-1,0
  4833.3    0.12       0  4877.5    0.05       0  5513.2    0.03       0
  5517.2    0.05       0
Bank Sta=5513.2,5517.2
Exp/Cntr=0.3,0.1

Type RM Length L Ch R = 1,192,0,0,0
BEGIN DESCRIPTION:
HICKORY12 9.0
END DESCRIPTION:
XS GIS Cut Line= 3
      2737222.85     10215982.62      2737575.00     10216255.00
      2737780.67     10216378.10
#Sta/Elev= 30
  4554.8 1216.54  4585.1 1215.34  4599.6 1214.05  4634.9 1213.12  4699.2 1213.30
  4728.1 1212.47  4742.6 1213.04  4821.4 1213.64  4849.2 1212.24  4892.0 1212.91
  4927.3 1212.55  4956.3 1211.82  4970.8 1210.49  4977.1 1211.35  4985.3 1208.10
  4991.6 1209.02  4997.3 1208.11  5006.3 1208.08  5021.9 1208.96  5027.7 1208.48
  5099.2 1207.44  5099.6 1206.94  5103.7 1206.94  5104.0 1207.44  5117.2 1210.85
  5129.0 1212.27  5152.3 1213.18  5187.3 1215.71  5218.3 1216.34  5239.7 1215.74
#Mann=3,-1,0
  4554.8    0.05       0  5099.2    0.03       0  5104.0    0.05       0
Bank Sta=5099.2,5104
Exp/Cntr=0.3,0.1

Chan Stop Cuts=-1