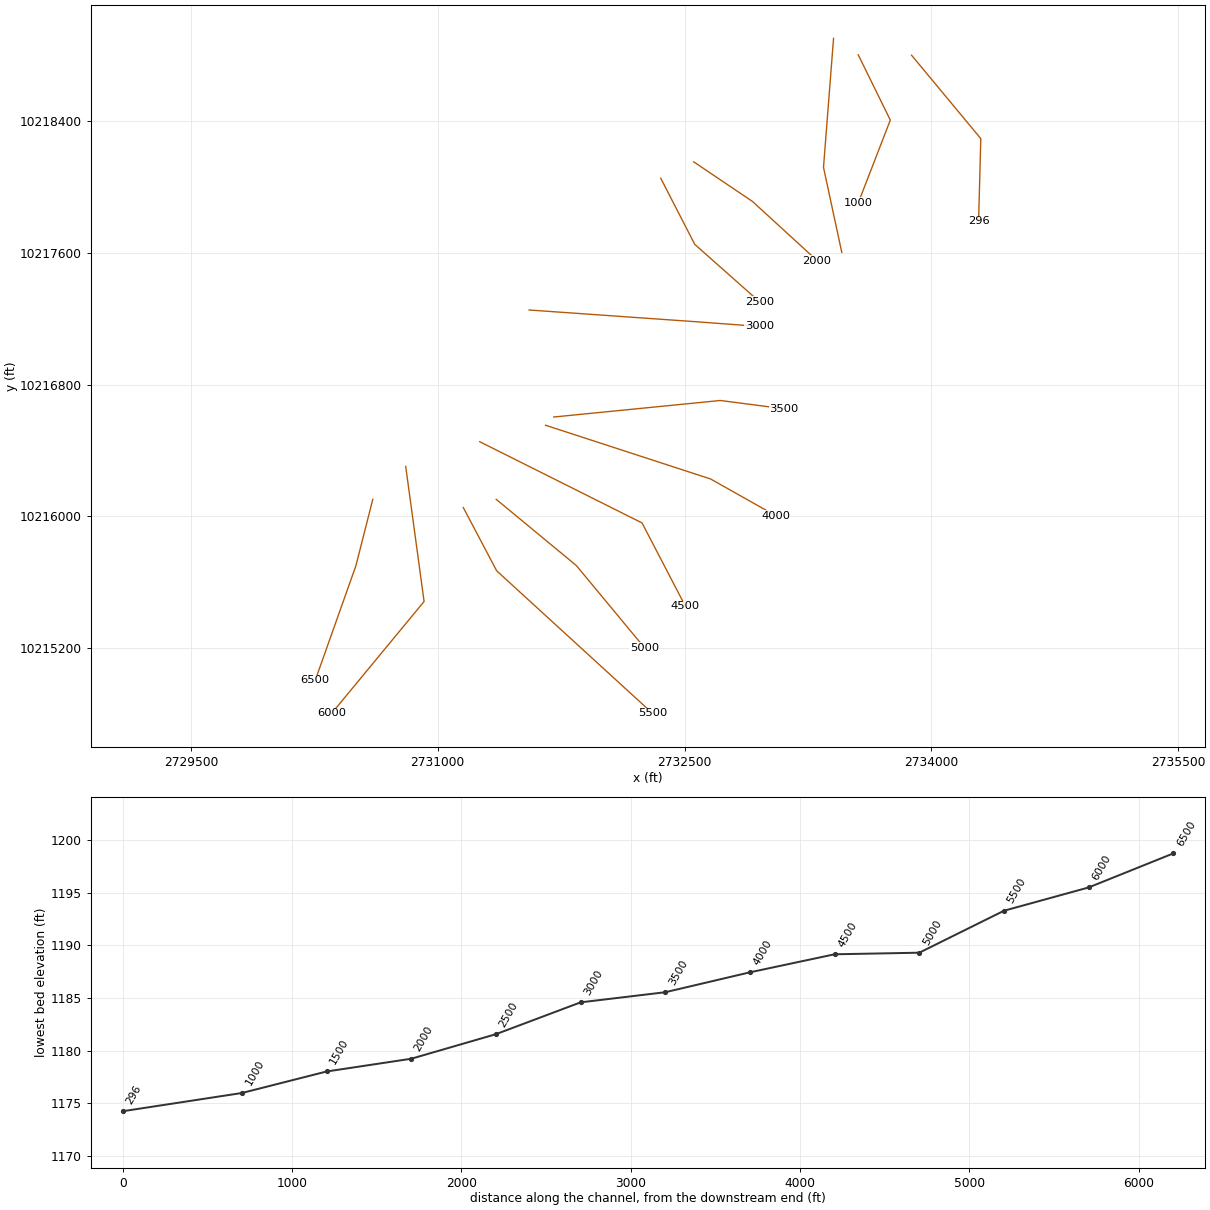
HEC-RAS study HICKORY13.prj: HICKORY13 Base Level Engineering

--- HICKORY13.g01 (geometry) --- (continued)

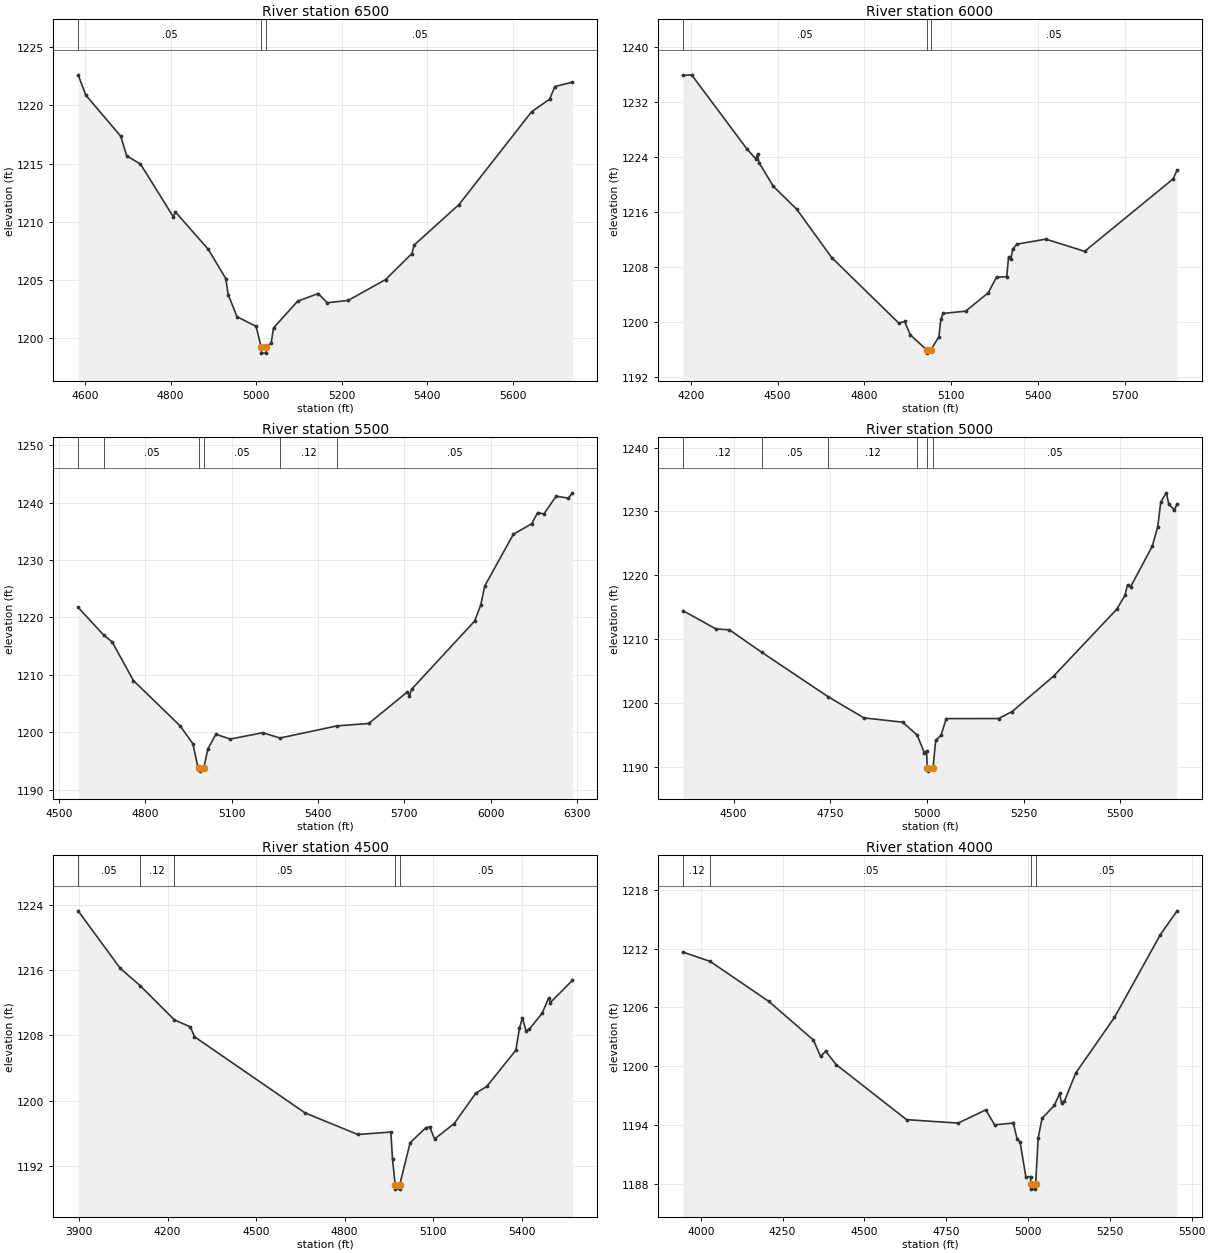
Type RM Length L Ch R = 1 ,6500    ,500,500,500
BEGIN DESCRIPTION:
HICKORY13 13.0
END DESCRIPTION:
XS GIS Cut Line= 3
      2730605.68     10216103.11      2730503.12     10215699.95
      2730255.67     10215003.08
#Sta/Elev= 30
    4584 1222.63  4601.9 1220.89  4683.7 1217.35  4697.5 1215.67  4729.8 1214.96
  4806.5 1210.43  4811.6 1210.84  4888.3 1207.63  4929.2 1205.12  4934.8 1203.74
  4955.5 1201.84    5000 1201.01    5012 1199.21  5012.5 1198.71  5023.3 1198.71
  5023.8 1199.21  5035.5 1199.61  5040.8 1200.88  5097.2 1203.17  5145.2 1203.83
  5166.4 1203.04  5215.3 1203.24  5302.6 1205.03  5364.3 1207.27  5369.6    1208
  5474.2 1211.47    5644 1219.45  5686.4 1220.54  5698.5 1221.62  5739.5    1222
#Mann= 3 ,-1 , 0
    4584     .05       0    5012     .03       0  5023.8     .05       0
Bank Sta=5012,5023.8
XS Rating Curve= 0 ,0
Exp/Cntr=0.3,0.1

Type RM Length L Ch R = 1 ,6000    ,500,500,500
BEGIN DESCRIPTION:
HICKORY13 12.0
END DESCRIPTION:
XS GIS Cut Line= 3
      2730805.68     10216303.11       2730917.4     10215482.68
      2730355.66     10214803.09
#Sta/Elev= 30
    4172 1235.85  4202.3 1235.94    4394 1225.14  4424.3 1223.73  4430.4 1224.38
  4435.4 1223.18  4484.9 1219.73  4565.6 1216.41  4686.7 1209.38  4918.8 1199.85
    4939 1200.08  4959.2  1198.1  5015.2 1195.98  5015.7 1195.48    5030 1195.98
  5057.7 1197.87  5064.3 1200.39  5072.1 1201.25  5150.2 1201.58  5228.4 1204.25
  5257.1 1206.54  5292.2 1206.58  5298.7 1209.46  5306.5 1209.19    5313  1210.6
  5327.4 1211.32  5427.6 1212.05  5561.9 1210.28    5868 1220.81  5881.7  1222.1
#Mann= 3 ,-1 , 0
    4172     .05       0  5015.2     .03       0    5030     .05       0
Bank Sta=5015.2,5030
XS Rating Curve= 0 ,0
Exp/Cntr=0.3,0.1

Type RM Length L Ch R = 1 ,5500    ,500,500,500
BEGIN DESCRIPTION:
HICKORY13 11.0
END DESCRIPTION:
XS GIS Cut Line= 3
       2731155.7     10216053.08       2731358.3     10215669.27
      2732305.72     10214803.08
#Sta/Elev= 30
    4566 1221.76  4654.9 1216.94  4684.2 1215.75  4758.2 1209.02  4920.8 1201.13
  4964.8 1198.03  4981.2 1194.23  4987.6 1193.77  4988.1 1193.27  5002.4 1193.77
  5016.7  1197.1    5045 1199.69  5094.4 1198.85  5207.8 1199.95  5267.6 1199.03
  5465.4 1201.14    5576 1201.56  5710.4 1207.06  5717.2  1206.3  5724.6  1207.5
  5944.2 1219.39  5965.1 1222.16  5979.3  1225.5  6078.6 1234.48  6142.1  1236.3
  6163.1 1238.25  6184.7 1238.02  6227.2  1241.1  6269.8 1240.77  6283.7 1241.69
#Mann= 6 ,-1 , 0
    4566     .12       0  4654.9     .05       0  4987.6     .05       0
  5002.4     .05       0  5267.6     .12       0  5465.4     .05       0
Bank Sta=4987.6,5002.4
XS Rating Curve= 0 ,0
Exp/Cntr=0.3,0.1

Type RM Length L Ch R = 1 ,5000    ,500,500,500
BEGIN DESCRIPTION:
HICKORY13 10.0
END DESCRIPTION:
XS GIS Cut Line= 3
      2731355.72     10216103.09      2731842.53       10215701.
       2732255.7      10215203.1
#Sta/Elev= 30
  4368.6 1214.44  4453.9 1211.58  4489.1 1211.43  4573.2 1207.89  4744.4 1200.95
  4836.9 1197.63  4937.2 1196.96  4974.8 1194.92  4993.2 1192.16  4998.8 1192.46
  5000.9 1189.79  5001.4 1189.29  5015.7 1189.79  5022.6 1194.14  5036.2 1194.88
  5049.9 1197.52  5185.3 1197.53  5220.5 1198.63  5327.3 1204.16    5491 1214.67
  5512.2 1216.84  5518.7 1218.49  5526.5 1218.16  5582.5  1224.5  5596.8 1227.55
  5604.7 1231.45    5619  1232.9  5625.5 1231.16  5639.8  1230.2    5647 1231.17
#Mann= 6 ,-1 , 0
  4368.6     .12       0  4573.2     .05       0  4744.4     .12       0
  4974.8     .05       0  5000.9     .05       0  5015.7     .05       0
Bank Sta=5000.9,5015.7
XS Rating Curve= 0 ,0
Exp/Cntr=0.3,0.1

Type RM Length L Ch R = 1 ,4500    ,500,500,500
BEGIN DESCRIPTION:
HICKORY13 9.0
END DESCRIPTION:
XS GIS Cut Line= 3
      2731255.66     10216453.12      2732241.92     10215959.72
       2732505.7     10215453.07
#Sta/Elev= 30
  3897.2 1223.27  4039.8 1216.22    4108 1214.07  4223.1  1209.9  4277.4 1209.03
  4291.3 1207.83  4665.7 1198.49  4844.6 1195.84  4956.4 1196.14    4962  1192.8
  4971.2 1189.64  4971.7 1189.14  4985.7 1189.14  4986.2 1189.64  5021.7 1194.83
  5075.1 1196.68    5088 1196.77  5104.4 1195.29  5170.7 1197.17  5244.2 1200.91
  5281.2 1201.73  5379.5 1206.16  5391.8 1208.86    5402 1210.15  5413.9 1208.59
  5424.6 1208.72  5468.9 1210.72    5491  1212.6  5496.6 1212.02  5571.2 1214.74
#Mann= 5 ,-1 , 0
  3897.2     .05       0    4108     .12       0  4223.1     .05       0
  4971.2     .05       0  4986.2     .05       0
Bank Sta=4971.2,4986.2
XS Rating Curve= 0 ,0
Exp/Cntr=0.3,0.1

Type RM Length L Ch R = 1 ,4000    ,500,500,500
BEGIN DESCRIPTION:
HICKORY13 8.0
END DESCRIPTION:
XS GIS Cut Line= 3
      2731655.67     10216553.12       2732658.7     10216226.71
      2733055.66     10216003.13
#Sta/Elev= 30
  3945.2 1211.66  4028.6  1210.7  4208.1 1206.61  4344.4 1202.66  4365.9 1200.99
  4381.6 1201.53  4413.5 1200.16  4628.8 1194.53  4786.5 1194.18  4871.1 1195.53
  4897.7    1194  4954.8 1194.18  4966.9 1192.53  4975.8 1192.25  4993.5 1188.65
    5008 1188.72  5008.1 1187.93  5008.6 1187.43  5022.7 1187.43  5023.2 1187.93
    5031 1192.66    5043 1194.67  5080.6 1195.99  5096.6 1197.21  5102.3 1196.25
  5111.3 1196.42  5145.7 1199.29  5264.2 1204.98  5404.3 1213.43  5455.6 1215.87
#Mann= 4 ,-1 , 0
  3945.2     .12       0  4028.6     .05       0  5008.1     .03       0
  5023.2     .05       0
Bank Sta=5008.1,5023.2
XS Rating Curve= 0 ,0
Exp/Cntr=0.3,0.1

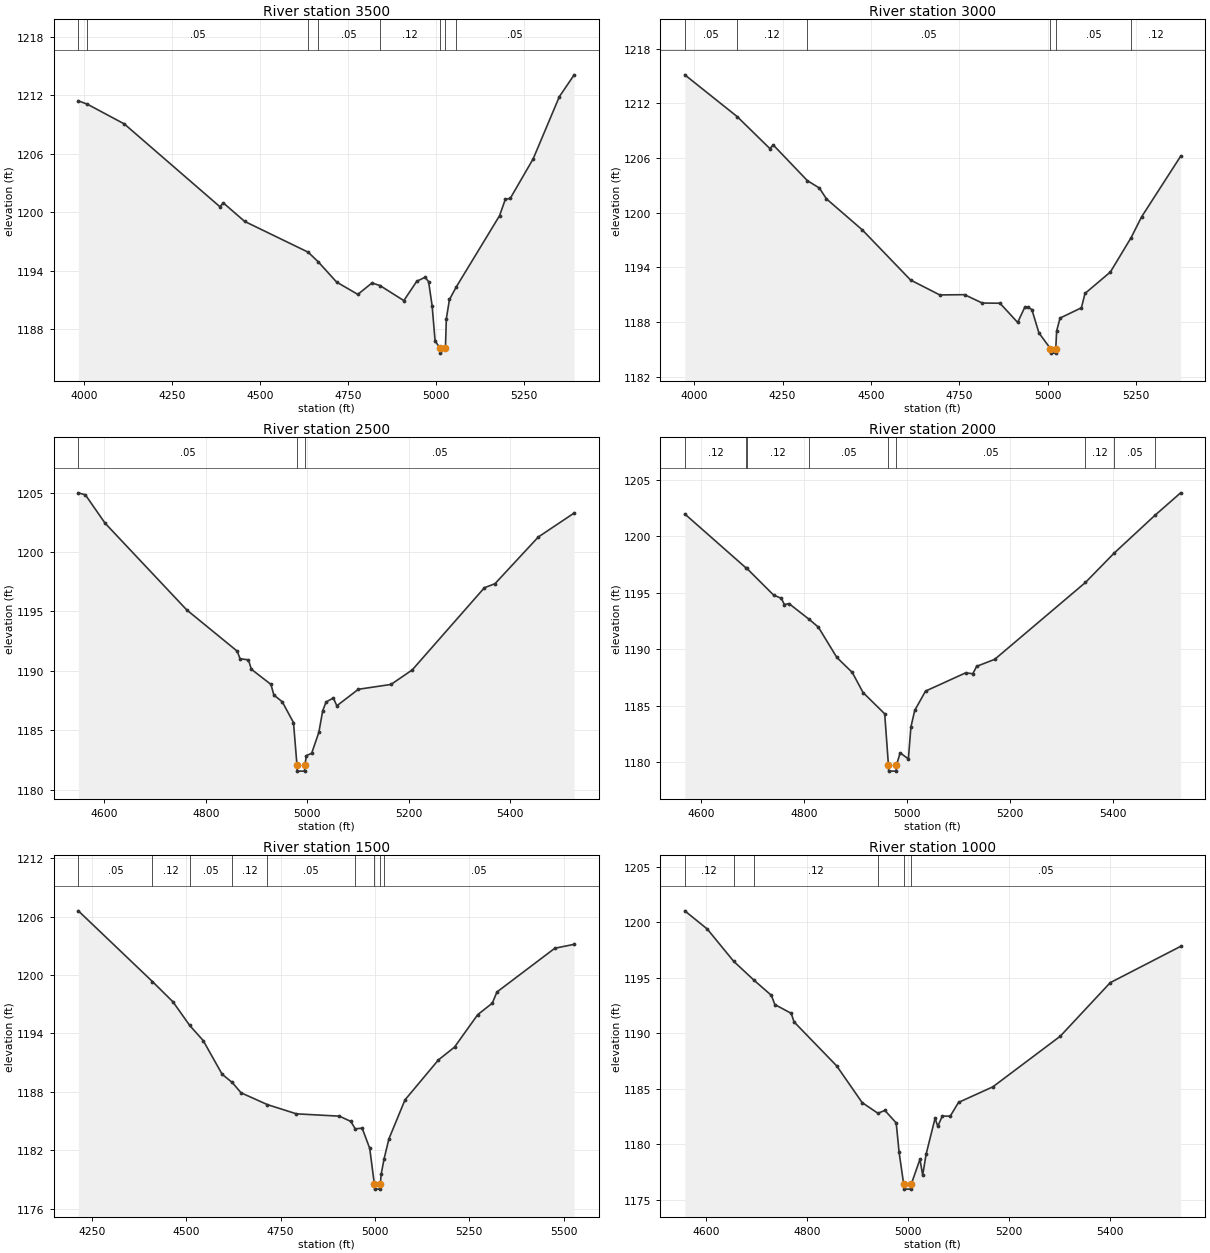
Type RM Length L Ch R = 1 ,3500    ,500,500,500
BEGIN DESCRIPTION:
HICKORY13 7.0
END DESCRIPTION:
XS GIS Cut Line= 3
      2731705.71     10216603.11      2732717.25     10216703.45
       2733105.7     10216653.11
#Sta/Elev= 30
  3983.5 1211.43  4009.5 1211.08  4114.1 1209.06  4385.4 1200.57  4395.5 1200.95
  4455.8 1199.06  4636.2  1195.9  4665.4 1194.89  4717.1 1192.83  4777.3 1191.57
  4817.5 1192.74    4840 1192.48    4908 1190.93  4944.6 1192.91  4968.3 1193.33
  4978.3 1192.87  4988.4 1190.38  4996.7  1186.8    5011 1186.04  5011.5 1185.54
  5026.1 1186.04  5028.7 1189.08  5037.6 1191.05    5057 1192.34  5179.9 1199.65
  5196.1 1201.32  5210.2 1201.42  5275.3 1205.48  5349.5 1211.85  5391.7  1214.1
#Mann= 8 ,-1 , 0
  3983.5     .12       0  4009.5     .05       0  4636.2     .12       0
  4665.4     .05       0    4840     .12       0    5011     .07       0
  5026.1     .12       0    5057     .05       0
Bank Sta=5011,5026.1
XS Rating Curve= 0 ,0
Exp/Cntr=0.3,0.1

Type RM Length L Ch R = 1 ,3000    ,500,500,500
BEGIN DESCRIPTION:
HICKORY13 6.0
END DESCRIPTION:
XS GIS Cut Line= 3
       2731555.7     10217253.11      2732580.07     10217181.09
      2732955.73     10217153.11
#Sta/Elev= 30
  3973.1 1215.14  4121.5 1210.55  4213.7 1207.05  4223.7 1207.43  4320.1 1203.52
    4354 1202.71  4374.1 1201.52  4475.7 1198.11  4612.2 1192.61  4694.9 1190.97
    4765    1191  4815.2 1190.08  4865.3 1190.06  4915.4 1187.95  4935.5 1189.62
  4945.5  1189.6  4955.5 1189.37  4975.6  1186.8  5008.1 1185.08  5008.6 1184.58
  5022.8 1184.58  5023.3 1185.08  5025.7 1187.01  5035.4 1188.43  5095.9 1189.56
  5105.9 1191.13  5177.9 1193.49  5236.5 1197.26  5266.3 1199.55  5376.7  1206.2
#Mann= 6 ,-1 , 0
  3973.1     .05       0  4121.5     .12       0  4320.1     .05       0
  5008.1     .03       0  5023.3     .05       0  5236.5     .12       0
Bank Sta=5008.1,5023.3
XS Rating Curve= 0 ,0
Exp/Cntr=0.3,0.1

Type RM Length L Ch R = 1 ,2500    ,500,500,500
BEGIN DESCRIPTION:
HICKORY13 5.0
END DESCRIPTION:
XS GIS Cut Line= 3
      2732355.67     10218053.13      2732562.11     10217651.93
      2732955.68     10217303.11
#Sta/Elev= 30
  4548.8 1204.99  4562.7 1204.82  4601.4 1202.44  4762.5 1195.13  4861.9 1191.66
  4867.5 1191.02  4884.1 1190.93  4889.7 1190.14  4928.4 1188.86  4934.1 1187.97
  4950.6  1187.4  4972.8 1185.65  4979.7 1182.06  4980.2 1181.56  4994.6 1181.56
  4995.1 1182.06  4998.4 1182.87  5008.6 1183.06  5022.8 1184.83  5030.4 1186.65
    5037 1187.38  5051.3 1187.72  5058.2 1187.06  5100.6 1188.45    5165 1188.86
  5206.8 1190.08    5349    1197  5369.9 1197.34  5455.2 1201.27  5525.9 1203.29
#Mann= 3 ,-1 , 0
  4548.8     .05       0  4979.7     .03       0  4995.1     .05       0
Bank Sta=4979.7,4995.1
XS Rating Curve= 0 ,0
Exp/Cntr=0.3,0.1

Type RM Length L Ch R = 1 ,2000    ,500,500,500
BEGIN DESCRIPTION:
HICKORY13 4.0
END DESCRIPTION:
XS GIS Cut Line= 3
       2732555.7      10218153.1      2732913.47     10217912.06
      2733305.71     10217553.09
#Sta/Elev= 30
  4568.6 1201.98  4687.7  1197.2    4689 1197.17    4741 1194.81    4756 1194.52
    4762 1193.97    4771 1194.05  4810.4 1192.65    4828 1191.97  4863.9 1189.29
  4893.9 1187.96  4914.9 1186.18  4956.9  1184.3  4964.2 1179.73  4964.7 1179.23
  4979.1 1179.23  4979.6 1179.73  4986.9 1180.85  5002.9 1180.31  5007.8 1183.13
  5015.2  1184.6  5036.2 1186.31  5113.9 1187.92  5128.1 1187.85  5135.5  1188.5
  5170.6 1189.12  5346.8 1195.92  5402.4 1198.51  5481.6 1201.85  5531.7 1203.85
#Mann= 9 ,-1 , 0
  4568.6     .12       0  4687.7     .05       0    4689     .12       0
  4810.4     .05       0  4964.2     .05       0  4979.6     .05       0
  5346.8     .12       0  5402.4     .05       0  5481.6     .12       0
Bank Sta=4964.2,4979.6
XS Rating Curve= 0 ,0
Exp/Cntr=0.3,0.1

Type RM Length L Ch R = 1 ,1500    ,500,500,500
BEGIN DESCRIPTION:
HICKORY13 3.0
END DESCRIPTION:
XS GIS Cut Line= 3
      2733405.68     10218903.11      2733344.62     10218119.49
      2733455.69     10217603.09
#Sta/Elev= 30
    4214 1206.59  4410.4 1199.33  4464.8 1197.25  4509.3 1194.82    4545 1193.27
  4595.2 1189.81  4621.9 1188.97  4645.3 1187.91  4714.9  1186.7    4792 1185.75
  4906.1 1185.51  4936.2 1184.97    4948 1184.21  4966.3 1184.28  4986.3 1182.21
  4998.7 1178.52  4999.2 1178.02  5013.8 1178.02  5014.3 1178.52  5016.7 1179.55
  5024.4 1181.13  5037.2 1183.18  5079.8 1187.18  5168.3 1191.28  5211.1  1192.6
  5272.5 1195.93  5311.2 1197.11  5323.6 1198.26    5477 1202.75  5528.2 1203.15
#Mann= 9 ,-1 , 0
    4214     .05       0  4410.4     .12       0  4509.3     .05       0
  4621.9     .12       0  4714.9     .05       0    4948     .12       0
  4998.7     .07       0  5014.3     .12       0  5024.4     .05       0
Bank Sta=4998.7,5014.3
XS Rating Curve= 0 ,0
Exp/Cntr=0.3,0.1

Type RM Length L Ch R = 1 ,1000    ,704,704,704
BEGIN DESCRIPTION:
HICKORY13 2.0
END DESCRIPTION:
XS GIS Cut Line= 3
       2733555.7     10218803.09      2733750.64      10218406.4
       2733555.7     10217903.14
#Sta/Elev= 30
    4558 1201.04  4602.5  1199.4  4654.7  1196.5  4694.8  1194.8  4729.4 1193.43
  4736.3  1192.6  4768.7 1191.81  4774.3 1191.04  4858.7 1187.08  4909.2 1183.77
  4940.5 1182.81  4954.1 1183.07  4976.6 1181.94  4982.2 1179.33  4991.2 1176.48
  4991.7 1175.98  5006.3 1175.98  5006.8 1176.48  5023.6 1178.67    5029 1177.23
  5035.7 1179.11  5053.5 1182.36  5058.9 1181.64  5067.9 1182.56  5083.5 1182.55
    5100 1183.79  5167.9 1185.19  5301.4 1189.75  5400.3 1194.57  5539.7 1197.84
#Mann= 6 ,-1 , 0
    4558     .12       0  4654.7     .05       0  4694.8     .12       0
  4940.5     .05       0  4991.2     .05       0  5006.8     .05       0
Bank Sta=4991.2,5006.8
XS Rating Curve= 0 ,0
Exp/Cntr=0.3,0.1

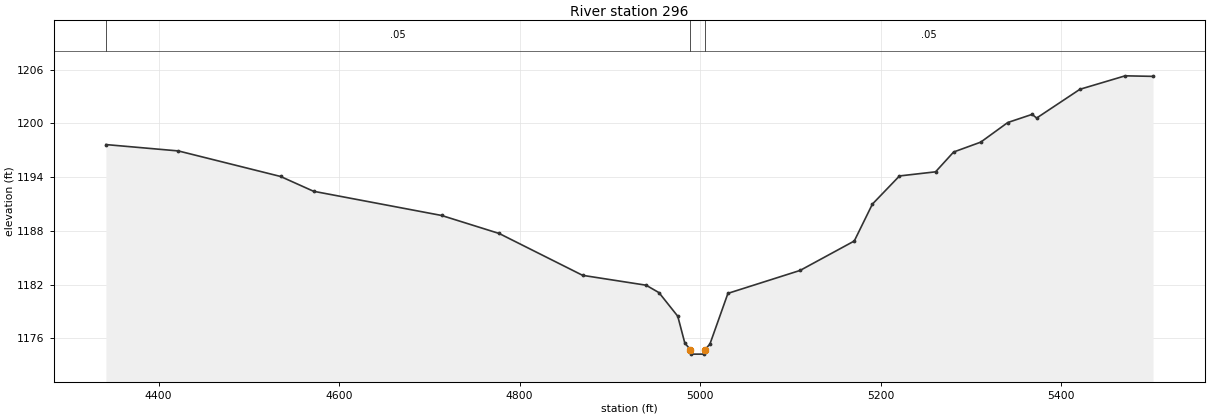
Type RM Length L Ch R = 1 ,296     ,0,0,0
BEGIN DESCRIPTION:
HICKORY13 1.0
END DESCRIPTION:
XS GIS Cut Line= 3
      2733879.81     10218800.47       2734300.5       10218294.
      2734287.18     10217792.18
#Sta/Elev= 30
  4341.6 1197.63  4421.9 1196.92  4535.2 1194.07  4571.7 1192.42  4713.6 1189.72
  4777.4 1187.71  4869.9 1183.04  4940.2 1181.94  4954.5 1181.11  4975.3 1178.48
  4983.1 1175.49  4989.3 1174.75  4989.8 1174.25  5004.8 1174.25  5005.3 1174.75
  5010.9 1175.36  5030.9 1181.03  5110.9 1183.59  5170.9 1186.87    5191 1190.99
    5221 1194.13    5261 1194.59    5281  1196.8    5311  1197.9    5341 1200.09
    5368    1201    5373 1200.59    5421  1203.8  5471.1  1205.3    5502 1205.24
#Mann= 3 ,-1 , 0
  4341.6     .05       0  4989.3     .05       0  5005.3     .05       0
Bank Sta=4989.3,5005.3
XS Rating Curve= 0 ,0
Exp/Cntr=0.3,0.1
Stream Node=HICKORY13       ,Reach-1         , 0 , 0 ,Upstream end
Stream Node=HICKORY13       ,Reach-1         , 0 , 1 ,Downstream end

Chan Stop Cuts=-1
Use User Specified Reach Order=0
Composite Channel Slope=5