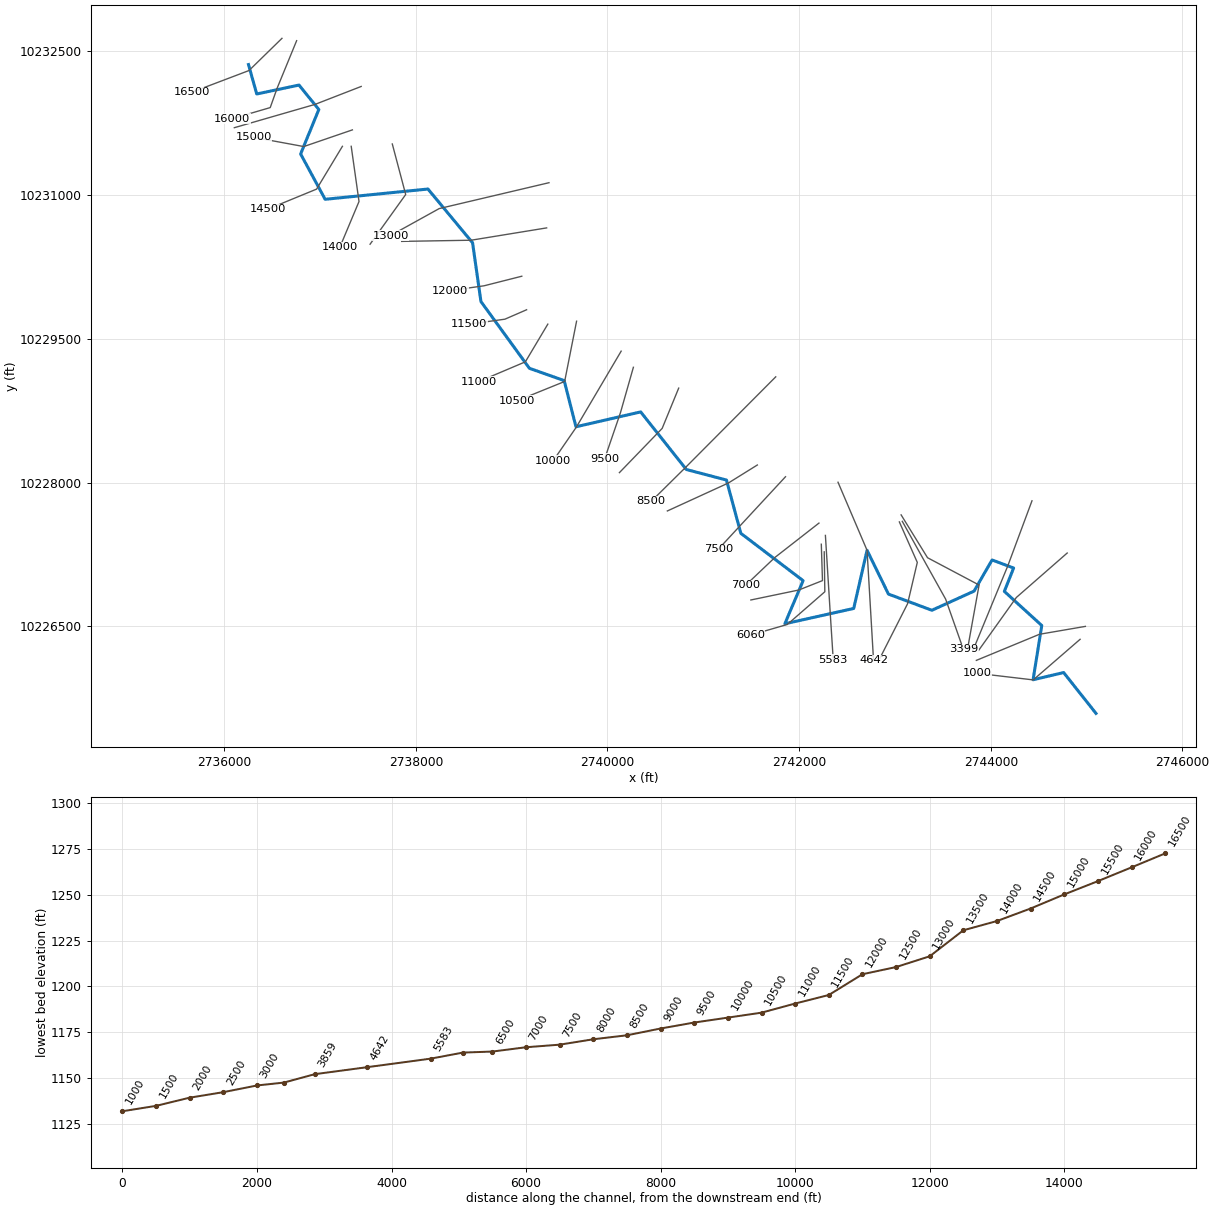
--- HICKORY14.prj (project) ---

Proj Title=HICKORY14 Base Level Engineering
Current Plan=p01
Default Exp/Contr=0.3,0.1
English Units
Geom File=g01
Flow File=f01
Plan File=p01
Y Axis Title=Elevation
X Axis Title(PF)=Main Channel Distance
X Axis Title(XS)=Station
BEGIN DESCRIPTION:
HICKORY14
END DESCRIPTION:
DSS Export Rating Curves= 0
DSS Export Rating Curve Sorted= 0
DSS Export Volume Flow Curves= 0
DXF OffsetX= 0
DXF OffsetY= 0
DXF ScaleX= 1
DXF ScaleY= 10

--- HICKORY14.p01 (plan) ---

Plan Title=Multiple Run
Short Identifier=Multiple
Geom File=g01
Flow File=f01
Subcritical Flow
K Sum by GR= 0
Std Step Tol= 0.01
Critical Tol= 0.01
Num of Std Step Trials= 20
Max Error Tol= 0.3
Flow Tol Ratio= 0.001
Split Flow NTrial= 30
Split Flow Tol= 0.02
Split Flow Ratio= 0.02
Log Output Level= 0
Friction Slope Method= 1
Unsteady Friction Slope Method= 2
Unsteady Bridges Friction Slope Method= 1
Parabolic Critical Depth
Global Vel Dist=  1 , 1 , 1
Global Log Level= 0
CheckData=True
Encroach Param= -1, 0, 0, 0
BEGIN DESCRIPTION:
Multiple Run
END DESCRIPTION:

--- HICKORY14.f01 (steady flow) ---

Flow Title=Multiple
Number of Profiles=7
Profile Names=10-year,25-year,50-year,1pct_min,100-year,1pct_plu,500-year
River Rch & RM= HICKORY14,Reach-1,16500
     424     685     915     686    1218    2162    1673
River Rch & RM= HICKORY14,Reach-1,11500
     532     875    1145     822    1534    2862    2107
River Rch & RM= HICKORY14,Reach-1,8500
     983    1676    2335    1650    3195    6188    4357
River Rch & RM= HICKORY14,Reach-1,2500
    1151    1983    2817    1970    3882    7648    5298
Boundary for River Rch & Prof#=HICKORY14,Reach-1,1
Up Type=0
Dn Type=3
Dn Slope=0.005
Boundary for River Rch & Prof#=HICKORY14,Reach-1,2
Up Type=0
Dn Type=3
Dn Slope=0.005
Boundary for River Rch & Prof#=HICKORY14,Reach-1,3
Up Type=0
Dn Type=3
Dn Slope=0.005
Boundary for River Rch & Prof#=HICKORY14,Reach-1,4
Up Type=0
Dn Type=3
Dn Slope=0.005
Boundary for River Rch & Prof#=HICKORY14,Reach-1,5
Up Type=0
Dn Type=3
Dn Slope=0.005
Boundary for River Rch & Prof#=HICKORY14,Reach-1,6
Up Type=0
Dn Type=3
Dn Slope=0.005
Boundary for River Rch & Prof#=HICKORY14,Reach-1,7
Up Type=0
Dn Type=3
Dn Slope=0.005

--- HICKORY14.g01 (geometry) ---

Geom Title=Existing Conditions
Program Version=4.10

River Reach=HICKORY14       ,Reach-1
Reach XY= 30
       2736253.5       10232362.       2736339.5       10232055.
      2736780.25       10232148.       2736987.5       10231893.
       2736797.5       10231429.      2737053.25       10230956.
      2738126.25       10231063.        2738592.       10230502.
      2738679.25       10229889.      2739185.25       10229192.
      2739547.75       10229064.        2739671.       10228582.
      2740346.25       10228737.      2740822.75       10228136.
       2741241.5       10228026.       2741391.5       10227470.
       2742041.5       10226976.      2741850.75       10226526.
       2742569.5       10226686.      2742708.75       10227293.
        2742932.       10226836.      2743385.25       10226667.
      2743825.75       10226867.      2744013.25       10227192.
      2744238.25       10227108.       2744141.5       10226864.
        2744532.       10226508.       2744441.5       10225942.
      2744760.25       10226017.      2745097.75       10225591.

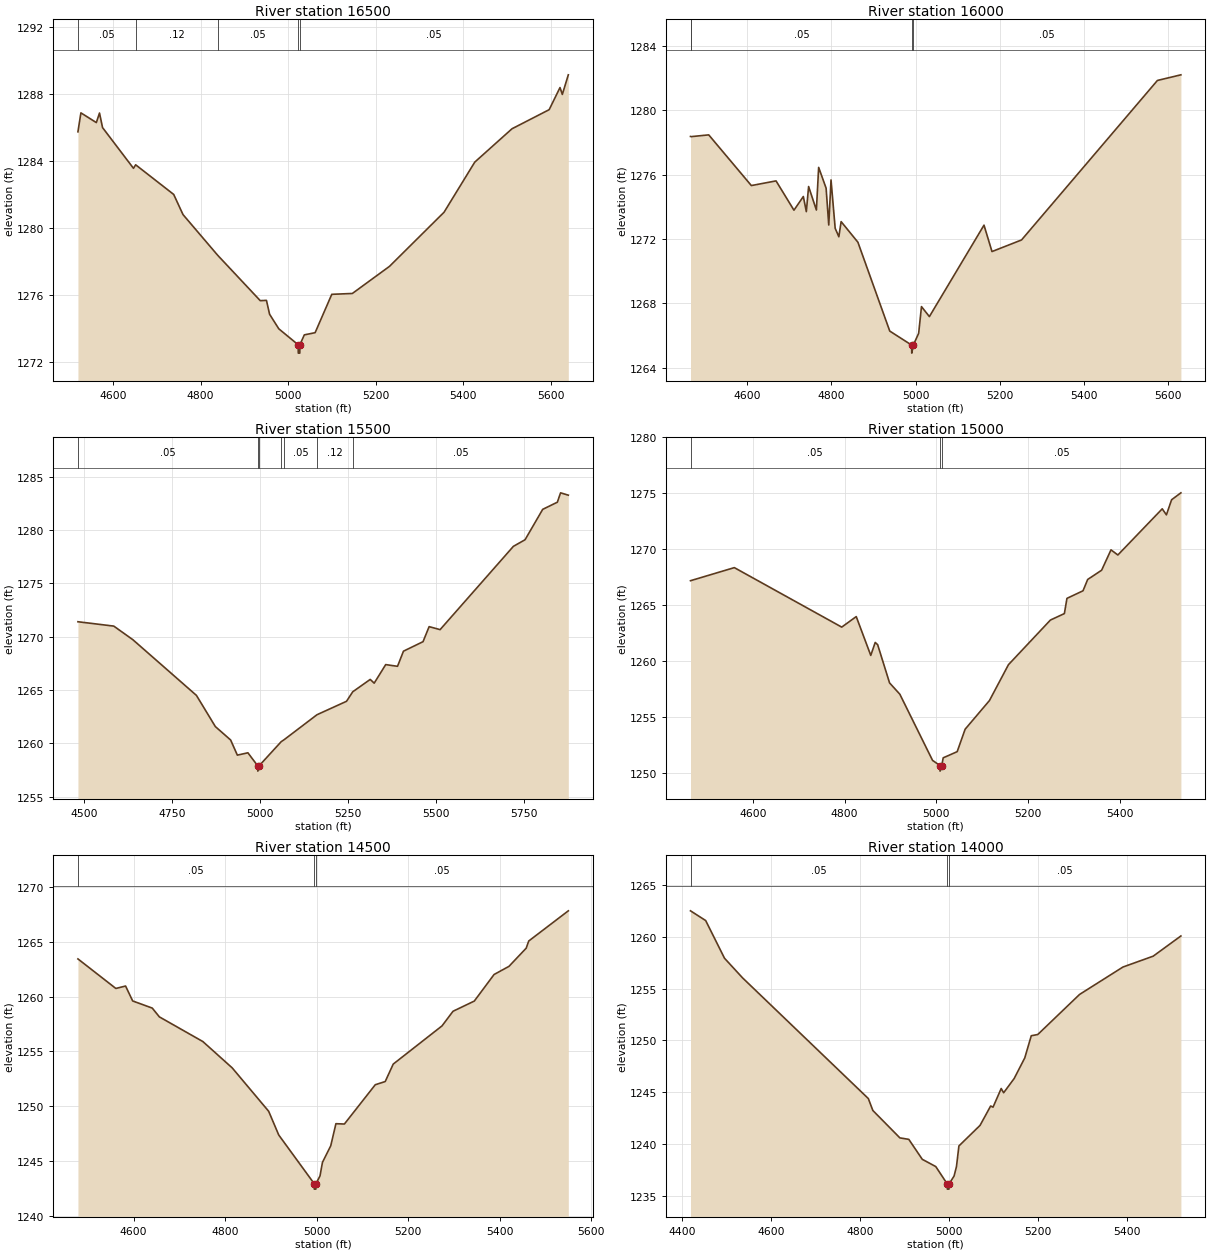
Type RM Length L Ch R = 1 ,16500   ,500,500,500
BEGIN DESCRIPTION:
HICKORY14 32.0
END DESCRIPTION:
XS GIS Cut Line= 3
      2736602.73     10232635.69      2736258.99      10232299.8
      2735660.09     10232072.44
#Sta/Elev= 30
  4519.4 1285.74  4526.2 1286.87  4561.5 1286.29  4568.7 1286.86  4575.7 1285.99
  4646.4 1283.56  4651.4 1283.77  4738.4    1282  4759.6  1280.8  4838.6 1278.38
  4936.3 1275.66  4950.4 1275.68  4957.6 1274.85  4978.7 1273.98  5022.9 1273.03
  5023.2 1272.53  5026.7 1272.53  5026.9 1273.03    5037 1273.62  5061.7 1273.75
  5099.8 1276.04  5146.8 1276.09  5231.8 1277.71  5356.5 1280.94  5426.7 1283.93
  5511.8 1285.92  5596.8 1287.06  5621.6 1288.38  5626.9 1287.97  5640.6 1289.14
#Mann= 5 ,-1 , 0
  4519.4     .05       0  4651.4     .12       0  4838.6     .05       0
  5022.9     .03       0  5026.9     .05       0
Bank Sta=5022.9,5026.9
XS Rating Curve= 0 ,0
Exp/Cntr=0.3,0.1

Type RM Length L Ch R = 1 ,16000   ,500,500,500
BEGIN DESCRIPTION:
HICKORY14 31.0
END DESCRIPTION:
XS GIS Cut Line= 4
      2736755.87     10232611.22      2736552.63     10232116.22
      2736480.26       10231913.      2736082.13     10231796.63
#Sta/Elev= 30
  4464.9 1278.37  4466.6 1278.36  4508.2 1278.47  4609.5 1275.32  4668.2 1275.61
  4710.8 1273.79  4733.1 1274.64  4740.2  1273.7  4745.6 1275.26  4764.1  1273.8
  4769.5 1276.45  4787.2 1275.16  4793.5 1272.87  4798.9 1275.67  4808.8 1272.66
  4817.5 1272.14  4822.9 1273.08  4862.8  1271.8  4938.5 1266.28  4990.5 1265.41
  4990.8 1264.91  4994.5 1265.41  5007.2 1266.14  5013.9  1267.8  5032.7 1267.18
  5162.5 1272.86  5181.5 1271.22  5251.7 1271.94  5574.7 1281.85  5630.5  1282.2
#Mann= 4 ,-1 , 0
  4464.9     .12       0  4466.6     .05       0  4990.5     .03       0
  4994.5     .05       0
Bank Sta=4990.5,4994.5
XS Rating Curve= 0 ,0
Exp/Cntr=0.3,0.1

Type RM Length L Ch R = 1 ,15500   ,500,500,500
BEGIN DESCRIPTION:
HICKORY14 30.0
END DESCRIPTION:
XS GIS Cut Line= 3
       2737429.6      10232133.5      2736948.07      10231946.4
       2736105.7     10231703.12
#Sta/Elev= 30
  4483.4  1271.4  4585.3 1270.99  4639.7 1269.71  4820.2 1264.49  4873.8 1261.57
  4917.3 1260.31  4936.4 1258.89  4966.3 1259.11  4994.2 1257.89  4994.5 1257.39
  4998.2 1257.89  5061.2 1260.16  5068.6 1260.32  5162.7 1262.68  5246.6 1263.94
  5264.2 1264.83  5313.9 1265.99  5325.2 1265.64  5357.9 1267.38  5391.5 1267.22
  5408.4 1268.64    5464 1269.53  5481.3 1270.94  5512.5 1270.66  5720.7 1278.47
  5753.9 1279.09    5804 1281.94  5845.6 1282.61  5854.8 1283.49  5876.8 1283.27
#Mann= 7 ,-1 , 0
  4483.4     .05       0  4994.2     .03       0  4998.2     .05       0
  5061.2     .12       0  5068.6     .05       0  5162.7     .12       0
  5264.2     .05       0
Bank Sta=4994.2,4998.2
XS Rating Curve= 0 ,0
Exp/Cntr=0.3,0.1

Type RM Length L Ch R = 1 ,15000   ,500,500,500
BEGIN DESCRIPTION:
HICKORY14 29.0
END DESCRIPTION:
XS GIS Cut Line= 3
      2737337.73     10231680.27      2736830.43     10231506.31
      2736305.68     10231603.11
#Sta/Elev= 30
  4463.7 1267.18  4559.3 1268.35  4793.6 1263.03  4825.3 1263.97    4857  1260.5
  4866.7 1261.66    4872 1261.46    4898 1258.04  4920.4 1257.03  4991.8 1251.11
  5007.9 1250.65  5008.2 1250.15  5011.9 1250.65    5015 1251.34  5045.5 1251.89
  5062.9  1253.9  5115.9 1256.46  5157.4 1259.67  5248.9 1263.66  5279.4 1264.24
    5285  1265.6  5320.1 1266.28  5330.2 1267.29  5360.7 1268.12  5381.1 1269.94
  5396.1 1269.48  5492.9 1273.61    5502 1273.07  5513.3 1274.42  5533.6 1275.04
#Mann= 3 ,-1 , 0
  4463.7     .05       0  5007.9     .05       0  5011.9     .05       0
Bank Sta=5007.9,5011.9
XS Rating Curve= 0 ,0
Exp/Cntr=0.3,0.1

Type RM Length L Ch R = 1 ,14500   ,500,500,500
BEGIN DESCRIPTION:
HICKORY14 28.0
END DESCRIPTION:
XS GIS Cut Line= 3
      2737233.57     10231508.75      2736964.18     10231062.22
       2736455.7     10230853.12
#Sta/Elev= 30
  4478.5 1263.43  4561.3 1260.74  4582.6 1260.96  4598.1  1259.6  4640.9 1258.95
  4656.4 1258.15  4751.5  1255.9  4815.6  1253.5  4895.2 1249.55  4917.2 1247.39
  4994.6 1242.96  4994.8 1242.46  4998.3 1242.46  4998.6 1242.96  5007.3 1243.66
  5012.7  1244.9  5030.8 1246.41  5042.1 1248.42  5060.6 1248.39  5128.1 1251.97
  5149.8 1252.26  5167.3 1253.85  5273.9 1257.33  5297.9 1258.66  5344.4 1259.59
  5387.6 1262.01  5420.1 1262.75  5457.8 1264.41  5463.3 1265.06  5549.8 1267.81
#Mann= 3 ,-1 , 0
  4478.5     .05       0  4994.6     .03       0  4998.6     .05       0
Bank Sta=4994.6,4998.6
XS Rating Curve= 0 ,0
Exp/Cntr=0.3,0.1

Type RM Length L Ch R = 1 ,14000   ,500,500,500
BEGIN DESCRIPTION:
HICKORY14 27.0
END DESCRIPTION:
XS GIS Cut Line= 3
      2737325.45     10231508.76      2737406.92       10230933.
      2737205.67     10230453.08
#Sta/Elev= 30
  4418.5 1262.52  4452.6 1261.58  4494.9 1257.94  4535.3 1256.05  4818.1 1244.38
  4828.2 1243.23    4889 1240.58    4909 1240.44  4939.3 1238.51  4969.6 1237.81
  4995.4 1236.13  4995.7 1235.63  4999.2 1235.63  4999.4 1236.13  5010.7 1236.89
  5016.1  1237.8  5021.6  1239.8  5069.1 1241.79  5092.9 1243.66  5098.3 1243.55
  5116.6 1245.35  5122.1 1244.94  5145.8 1246.32  5169.6 1248.31  5184.2 1250.45
  5198.8 1250.57  5292.7 1254.44  5390.2 1257.09  5458.2 1258.14  5520.4 1260.09
#Mann= 3 ,-1 , 0
  4418.5     .05       0  4995.4     .05       0  4999.4     .05       0
Bank Sta=4995.4,4999.4
XS Rating Curve= 0 ,0
Exp/Cntr=0.3,0.1

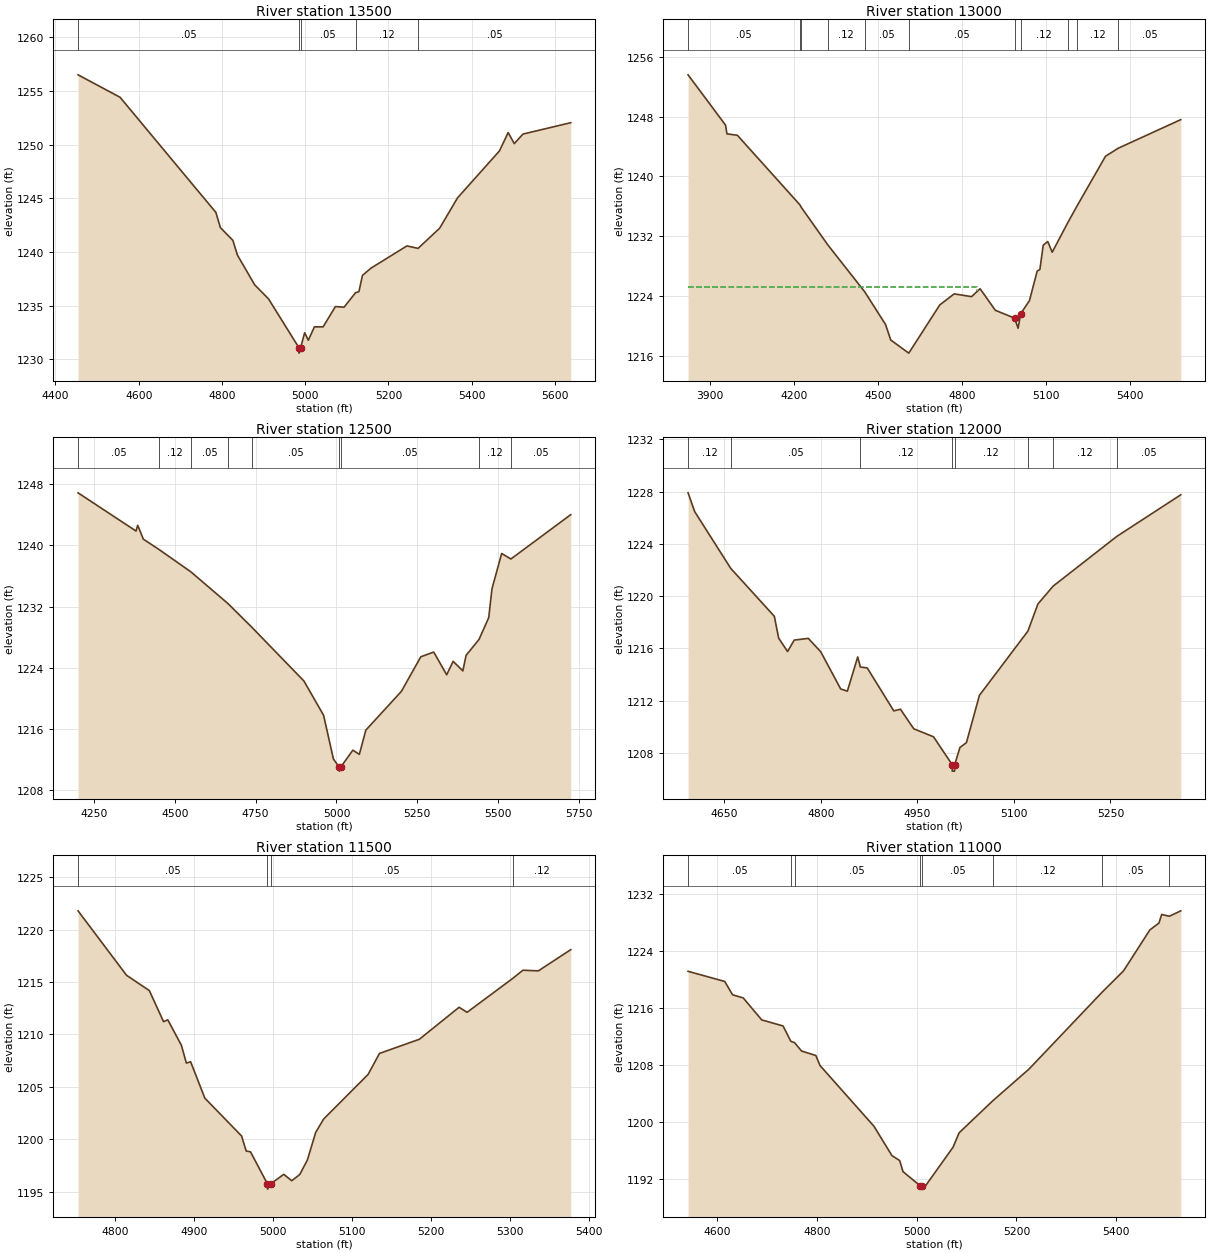
Type RM Length L Ch R = 1 ,13500   ,500,500,500
BEGIN DESCRIPTION:
HICKORY14 26.0
END DESCRIPTION:
XS GIS Cut Line= 3
      2737754.18     10231533.25      2737894.02     10231005.77
      2737522.22     10230487.05
#Sta/Elev= 30
  4454.3 1256.51  4555.2 1254.42  4785.5 1243.69  4796.4 1242.27  4826.3 1241.09
  4837.2 1239.72  4878.6 1236.95  4911.9 1235.64  4985.1 1231.08  4985.4 1230.58
  4989.1 1231.08  4998.8 1232.48  5007.6 1231.78  5022.3 1233.03  5043.2 1233.03
  5072.7 1234.92  5093.5 1234.86  5121.2 1236.21  5129.2 1236.31  5137.7 1237.82
  5158.6 1238.51  5244.6 1240.57  5271.3 1240.34  5323.2 1242.22  5366.2 1245.05
  5466.9 1249.42  5487.8 1251.13  5502.5  1250.1  5523.4 1250.99  5638.2 1252.05
#Mann= 5 ,-1 , 0
  4454.3     .05       0  4985.1     .03       0  4989.1     .05       0
  5121.2     .12       0  5271.3     .05       0
Bank Sta=4985.1,4989.1
XS Rating Curve= 0 ,0
Exp/Cntr=0.3,0.1

Type RM Length L Ch R = 1 ,13000   ,500,500,500
BEGIN DESCRIPTION:
HICKORY14 25.0
END DESCRIPTION:
XS GIS Cut Line= 3
      2739389.44     10231129.05      2738243.45     10230858.91
      2737736.03     10230577.96
#Sta/Elev= 30
  3822.6 1253.59  3956.2 1246.87  3961.3  1245.7  3998.5 1245.51  4221.3 1236.22
  4226.7 1235.86    4321 1230.86  4452.4  1224.6  4527.1 1220.21  4545.6 1218.14
  4609.8 1216.39  4720.3 1222.83  4771.7 1224.31  4833.8 1223.94  4864.1    1225
  4918.5 1222.12  4987.4 1221.06 4999.73 1219.72  5008.9 1221.66  5040.2  1223.4
  5067.7 1227.34  5077.5 1227.58  5089.4 1230.82  5105.5 1231.31  5121.5 1229.88
  5177.4 1233.86  5209.5 1236.03  5311.6 1242.71    5357 1243.78    5580  1247.6
#Mann= 11 ,-1 , 0
  3822.6     .05       0  4221.3     .12       0  4226.7     .05       0
    4321     .12       0  4452.4     .05       0  4609.8     .05       0
  4987.4     .05       0  5008.9     .12       0  5177.4     .05       0
  5209.5     .12       0    5357     .05       0
#XS Ineff= 2 , 0
         4853.69 1225.24
Permanent Ineff=
       F       F
Bank Sta=4987.4,5008.9
XS Rating Curve= 0 ,0
Exp/Cntr=0.3,0.1

Type RM Length L Ch R = 1 ,12500   ,500,500,500
BEGIN DESCRIPTION:
HICKORY14 24.0
END DESCRIPTION:
XS GIS Cut Line= 3
      2739364.91     10230657.45      2738576.34     10230528.77
      2737852.14     10230516.59
#Sta/Elev= 30
    4201 1246.86  4380.3 1241.87  4385.4 1242.63  4402.9 1240.81    4450  1239.5
  4549.3 1236.56  4664.8 1232.39  4737.8 1229.33  4899.3 1222.29  4960.1 1217.82
  4990.5 1212.11  5008.7 1211.02  5008.9 1210.52  5012.7 1211.02  5050.7 1213.26
  5070.7 1212.71  5090.7 1215.87  5200.7 1220.94  5260.7 1225.45  5300.7 1226.07
  5340.7  1223.1  5360.7 1224.86  5390.7 1223.61  5400.7 1225.64  5440.6 1227.71
  5470.7 1230.56  5480.7 1234.32  5510.7 1238.94  5539.3 1238.22  5724.3 1244.01
#Mann= 9 ,-1 , 0
    4201     .05       0    4450     .12       0  4549.3     .05       0
  4664.8     .12       0  4737.8     .05       0  5008.7     .05       0
  5012.7     .05       0  5440.6     .12       0  5539.3     .05       0
Bank Sta=5008.7,5012.7
XS Rating Curve= 0 ,0
Exp/Cntr=0.3,0.1

Type RM Length L Ch R = 1 ,12000   ,500,500,500
BEGIN DESCRIPTION:
HICKORY14 23.0
END DESCRIPTION:
XS GIS Cut Line= 3
      2739105.64      10230153.1      2738711.52     10230053.16
      2738355.72     10230003.12
#Sta/Elev= 30
  4593.4  1227.9  4603.7 1226.46  4659.7 1222.12  4727.5 1218.45  4734.2 1216.78
  4748.1 1215.75  4758.4 1216.63  4780.3 1216.76  4799.7 1215.73  4830.6 1212.89
    4841 1212.72  4857.1 1215.34  4861.2 1214.57  4871.9  1214.5  4913.2 1211.21
  4923.5 1211.34  4944.2 1209.84  4974.9 1209.23  5003.9  1207.1  5004.1  1206.6
  5007.6  1206.6  5007.9  1207.1    5016 1208.41  5026.1 1208.78  5046.3  1212.4
  5121.7 1217.32  5137.2 1219.39  5160.9 1220.76    5260 1224.57  5359.3 1227.75
#Mann= 8 ,-1 , 0
  4593.4     .12       0  4659.7     .05       0  4861.2     .12       0
  5003.9     .07       0  5007.9     .12       0  5121.7     .05       0
  5160.9     .12       0    5260     .05       0
Bank Sta=5003.9,5007.9
XS Rating Curve= 0 ,0
Exp/Cntr=0.3,0.1

Type RM Length L Ch R = 1 ,11500   ,500,500,500
BEGIN DESCRIPTION:
HICKORY14 22.0
END DESCRIPTION:
XS GIS Cut Line= 3
      2739155.73     10229803.13       2738929.3      10229704.7
      2738555.64     10229653.11
#Sta/Elev= 30
  4753.1 1221.78  4814.5 1215.64  4843.4 1214.18  4861.4 1211.22  4866.8 1211.39
    4884 1208.97  4890.3 1207.27  4895.7  1207.4  4913.7 1203.93  4960.3 1200.32
  4966.1 1198.89  4971.5 1198.82    4993 1195.76  4993.2 1195.26    4997 1195.76
  5013.7 1196.67  5023.8 1196.06  5033.9 1196.65  5043.6 1198.04  5054.1 1200.66
  5064.2 1201.94  5120.5 1206.19  5134.9 1208.19  5185.4 1209.54  5235.8 1212.59
  5245.9 1212.11  5303.9 1215.35  5316.6 1216.12  5336.2 1216.06  5377.2 1218.08
#Mann= 4 ,-1 , 0
  4753.1     .05       0    4993     .05       0    4997     .05       0
  5303.9     .12       0
Bank Sta=4993,4997
XS Rating Curve= 0 ,0
Exp/Cntr=0.3,0.1

Type RM Length L Ch R = 1 ,11000   ,500,500,500
BEGIN DESCRIPTION:
HICKORY14 21.0
END DESCRIPTION:
XS GIS Cut Line= 3
      2739377.22     10229653.06      2739142.94     10229259.74
      2738655.65      10229053.1
#Sta/Elev= 30
  4542.2 1221.13  4615.7  1219.7  4631.3 1217.84  4652.7  1217.4  4689.7 1214.32
  4732.5 1213.47  4748.1 1211.32  4755.6 1211.13  4769.5 1209.96  4798.2 1209.33
  4806.5 1207.93  4914.6 1199.42  4950.6 1195.31  4966.2 1194.61  4972.8 1193.06
  5006.7 1191.11  5006.9 1190.61  5010.8 1191.11  5018.7 1191.15  5073.1 1196.49
  5085.2  1198.5  5152.7 1202.99  5225.1 1207.42  5371.8 1218.21  5414.6 1221.19
  5467.4 1226.93  5485.6 1227.89    5491 1229.09  5506.5 1228.84  5529.3  1229.6
#Mann= 8 ,-1 , 0
  4542.2     .05       0  4748.1     .12       0  4755.6     .05       0
  5006.7     .05       0  5010.8     .05       0  5152.7     .12       0
  5371.8     .05       0  5506.5     .12       0
Bank Sta=5006.7,5010.8
XS Rating Curve= 0 ,0
Exp/Cntr=0.3,0.1

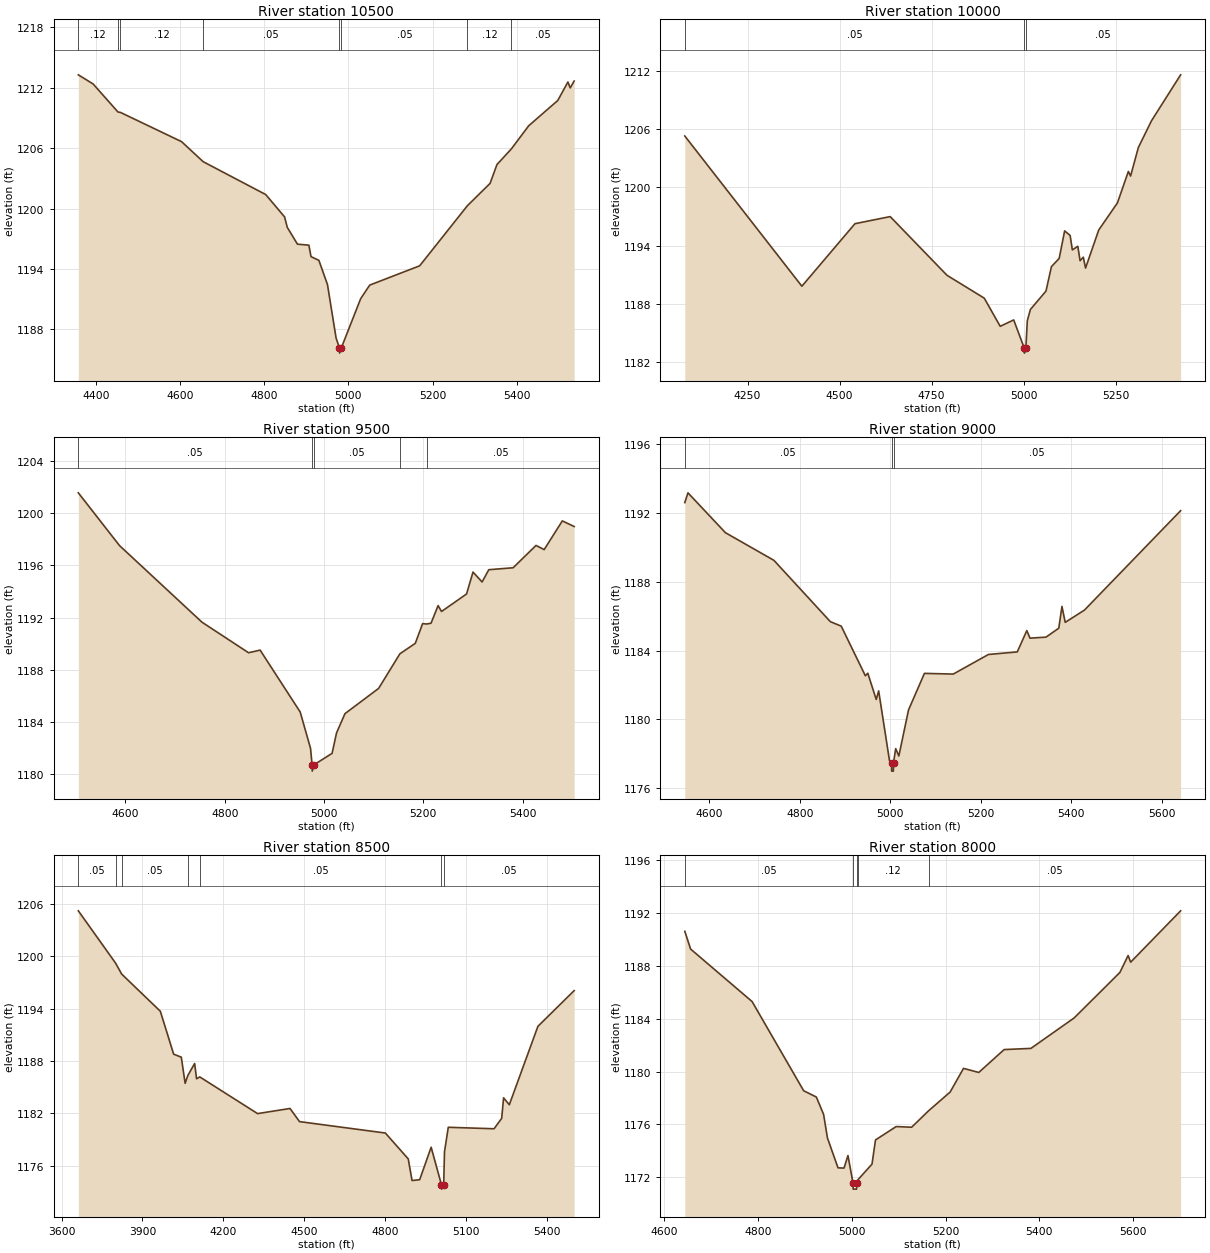
Type RM Length L Ch R = 1 ,10500   ,500,500,500
BEGIN DESCRIPTION:
HICKORY14 20.0
END DESCRIPTION:
XS GIS Cut Line= 3
      2739677.31     10229683.68      2739552.79     10229054.59
      2739055.67     10228853.11
#Sta/Elev= 30
  4358.7 1213.29  4393.9 1212.38    4453 1209.59  4458.4 1209.56  4603.9 1206.65
  4655.1 1204.66  4803.8 1201.39  4848.6 1199.17    4855 1198.13  4879.2 1196.46
  4906.3 1196.36  4911.4 1195.22  4930.1 1194.85  4950.5 1192.44  4970.9 1187.14
    4979 1186.13  4979.3 1185.63  4983.2 1186.13  5029.3 1191.04  5050.8 1192.39
  5169.5 1194.31  5282.8 1200.28  5336.7  1202.5    5353 1204.37  5387.5 1205.94
  5428.5 1208.23  5497.5 1210.74  5521.6 1212.58    5527 1211.99  5536.4 1212.67
#Mann= 8 ,-1 , 0
  4358.7     .12       0    4453     .05       0  4458.4     .12       0
  4655.1     .05       0    4979     .05       0  4983.2     .05       0
  5282.8     .12       0  5387.5     .05       0
Bank Sta=4979,4983.2
XS Rating Curve= 0 ,0
Exp/Cntr=0.3,0.1

Type RM Length L Ch R = 1 ,10000   ,500,500,500
BEGIN DESCRIPTION:
HICKORY14 19.0
END DESCRIPTION:
XS GIS Cut Line= 3
      2740142.77     10229371.28       2739675.1     10228578.55
      2739433.04     10228227.03
#Sta/Elev= 30
  4079.6 1205.29  4397.7 1189.82    4542 1196.26  4637.7 1196.99  4791.9 1190.95
  4893.3 1188.59  4936.6 1185.69  4973.3 1186.35  5002.1 1183.43  5002.3 1182.93
  5006.3 1183.43  5010.2 1186.26  5018.7 1187.43    5061 1189.32  5075.8 1191.84
  5096.8 1192.68  5111.7 1195.52  5126.6 1195.05  5132.6 1193.56  5147.5 1193.93
  5153.6 1192.45  5162.4 1192.81  5168.5 1191.69  5204.3 1195.61  5255.1  1198.4
  5284.8 1201.64  5290.9 1201.17  5311.9  1204.1  5347.7 1206.86  5426.8 1211.59
#Mann= 3 ,-1 , 0
  4079.6     .05       0  5002.1     .05       0  5006.3     .05       0
Bank Sta=5002.1,5006.3
XS Rating Curve= 0 ,0
Exp/Cntr=0.3,0.1

Type RM Length L Ch R = 1 ,9500    ,500,500,500
BEGIN DESCRIPTION:
HICKORY14 18.0
END DESCRIPTION:
XS GIS Cut Line= 3
       2740270.2     10229202.82      2740134.72     10228726.93
      2739971.28     10228250.48
#Sta/Elev= 30
  4505.2 1201.56  4588.1 1197.52  4754.2 1191.65    4848 1189.31  4871.3 1189.51
    4952 1184.77  4972.8 1181.99  4975.9 1180.74  4976.2 1180.24  4980.3 1180.74
  5016.2  1181.6  5025.2 1183.17  5042.1 1184.64    5110 1186.58  5152.8 1189.23
  5183.8 1190.03  5198.5 1191.54  5206.4 1191.51  5215.5 1191.57  5229.7 1192.92
  5236.6 1192.47    5287 1193.81    5300 1195.49  5318.3 1194.73  5331.8 1195.67
  5380.8 1195.82  5426.9 1197.53  5443.3 1197.21  5479.9 1199.41  5503.7 1198.98
#Mann= 5 ,-1 , 0
  4505.2     .05       0  4975.9     .05       0  4980.3     .05       0
  5152.8     .12       0  5206.4     .05       0
Bank Sta=4975.9,4980.3
XS Rating Curve= 0 ,0
Exp/Cntr=0.3,0.1

Type RM Length L Ch R = 1 ,9000    ,500,500,500
BEGIN DESCRIPTION:
HICKORY14 17.0
END DESCRIPTION:
XS GIS Cut Line= 3
        2740743.     10228985.48      2740570.58     10228564.95
       2740124.4     10228103.49
#Sta/Elev= 30
  4545.5 1192.61  4552.5 1193.18  4635.3 1190.86  4742.6 1189.25  4867.4 1185.68
  4891.4 1185.42  4944.8 1182.53  4950.2 1182.68  4968.8 1181.15  4974.2 1181.65
  4998.2 1177.58  5002.6 1177.48  5002.9 1176.98  5006.7 1176.98    5007 1177.48
  5011.9 1178.29  5018.8 1177.86  5040.2 1180.54  5075.4 1182.67  5139.2 1182.63
  5216.9 1183.77  5280.7 1183.92  5301.8 1185.16  5308.8 1184.72  5344.2 1184.78
  5372.5  1185.3  5379.5 1186.57  5386.7 1185.64  5429.1 1186.35  5641.9 1192.14
#Mann= 3 ,-1 , 0
  4545.5     .05       0  5002.6     .03       0    5007     .05       0
Bank Sta=5002.6,5007
XS Rating Curve= 0 ,0
Exp/Cntr=0.3,0.1

Type RM Length L Ch R = 1 ,8500    ,500,500,500
BEGIN DESCRIPTION:
HICKORY14 16.0
END DESCRIPTION:
XS GIS Cut Line= 3
      2741755.68     10229103.11      2740811.97     10228155.03
      2740455.68     10227803.11
#Sta/Elev= 30
  3662.3 1205.24  3800.2 1199.25    3823 1197.98  3966.4 1193.71  4015.8 1188.78
  4044.1 1188.44  4058.3 1185.44  4068.4 1186.34  4093.6 1187.71  4100.7 1185.96
  4112.7 1186.17    4327 1181.96  4447.2 1182.55  4482.5 1181.04  4800.8 1179.73
  4885.6 1176.76  4899.7 1174.28    4928 1174.37  4970.5  1178.1  5008.8 1173.79
  5009.3 1173.29    5017 1173.79    5020 1177.57  5034.1 1180.39  5203.8 1180.22
  5232.1 1181.42  5239.1 1183.77  5260.4 1182.98  5366.4 1191.98  5500.8 1196.08
#Mann= 7 ,-1 , 0
  3662.3     .05       0  3800.2     .12       0    3823     .05       0
  4068.4     .12       0  4112.7     .05       0  5008.8     .05       0
    5017     .05       0
Bank Sta=5008.8,5017
XS Rating Curve= 0 ,0
Exp/Cntr=0.3,0.1

Type RM Length L Ch R = 1 ,8000    ,500,500,500
BEGIN DESCRIPTION:
HICKORY14 15.0
END DESCRIPTION:
XS GIS Cut Line= 3
      2741563.69     10228183.11      2741261.94     10227995.35
      2740624.71     10227703.45
#Sta/Elev= 30
  4644.6  1190.6    4657 1189.26    4788 1185.29  4897.8 1178.55  4924.9 1178.07
  4940.3 1176.76  4948.5 1174.98    4971 1172.72  4983.8  1172.7  4992.2 1173.65
  5002.8 1171.61  5003.3 1171.11  5010.5 1171.11    5011 1171.61  5013.7 1171.83
  5043.4    1173  5050.9 1174.83  5094.9 1175.84  5127.9 1175.79  5163.9 1177.03
  5209.9 1178.45  5238.4 1180.24  5270.9 1179.93  5324.9 1181.66    5382 1181.75
    5474 1184.05  5571.5 1187.49    5589 1188.77  5594.5 1188.27  5700.9 1192.15
#Mann= 5 ,-1 , 0
  4644.6     .05       0  5002.8     .05       0    5011     .05       0
  5013.7     .12       0  5163.9     .05       0
Bank Sta=5002.8,5011
XS Rating Curve= 0 ,0
Exp/Cntr=0.3,0.1

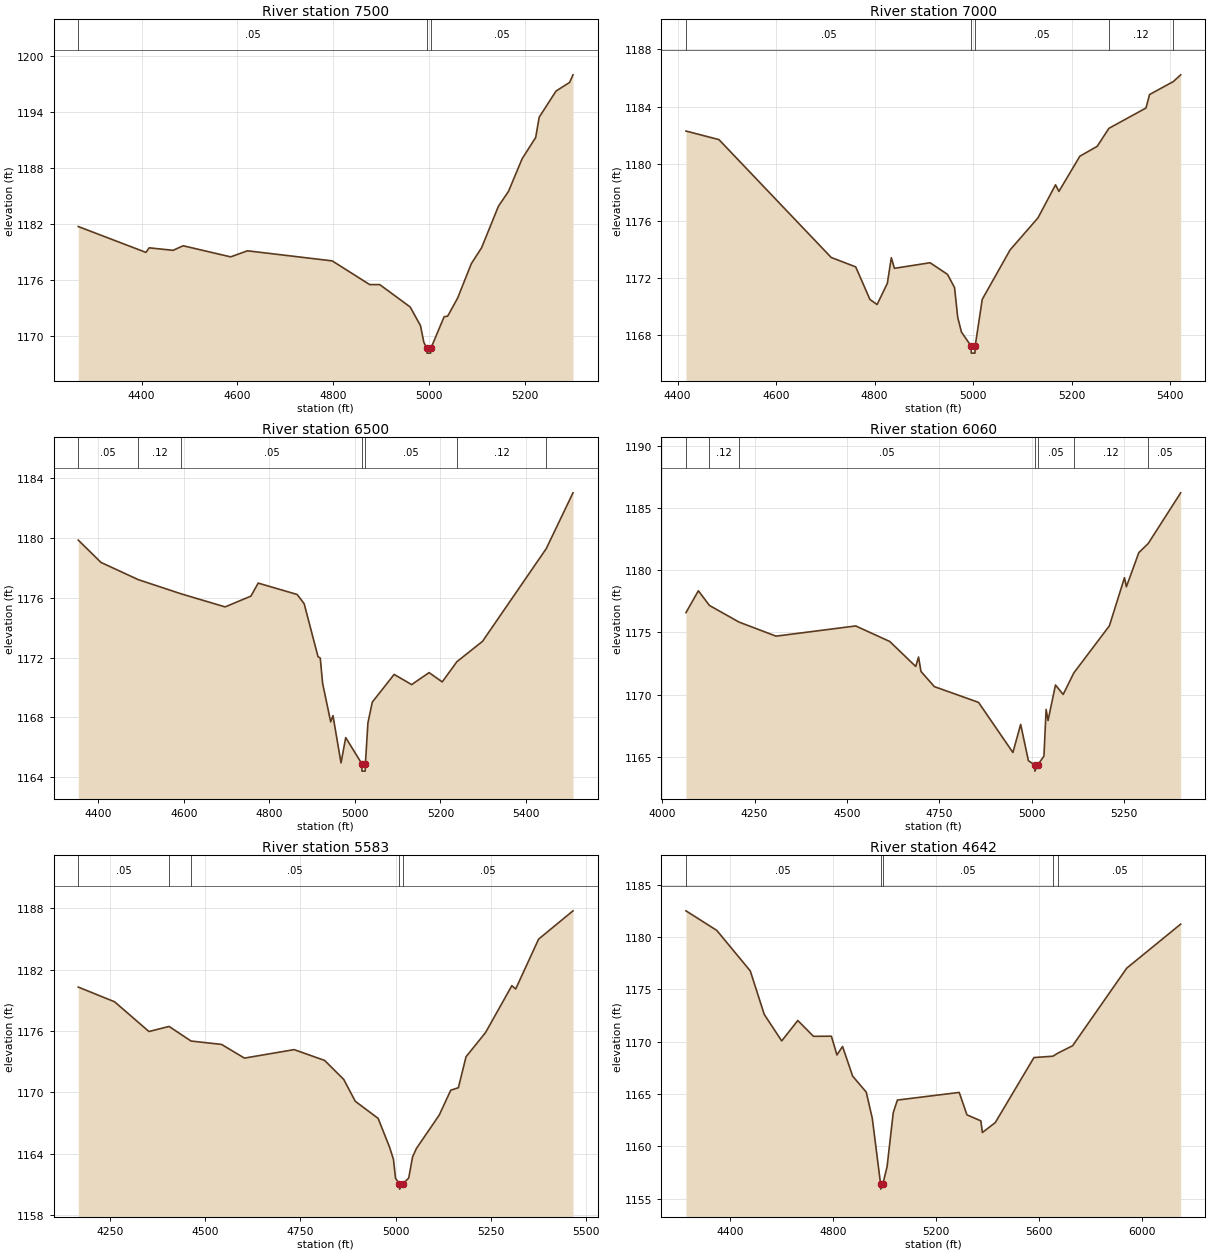
Type RM Length L Ch R = 1 ,7500    ,500,500,500
BEGIN DESCRIPTION:
HICKORY14 14.0
END DESCRIPTION:
XS GIS Cut Line= 3
      2741857.64     10228060.59      2741360.05     10227523.45
       2741155.7     10227303.13
#Sta/Elev= 30
  4267.8 1181.73    4409 1178.96  4415.8 1179.45  4465.7 1179.18  4486.7 1179.67
  4585.9 1178.48    4621 1179.13  4797.9 1178.05  4876.2 1175.51  4897.1 1175.51
  4960.7 1173.11  4982.2 1171.11    4989 1169.35  4995.3 1168.67  4995.8 1168.17
  5003.2 1168.17  5003.7 1168.67  5031.5 1172.07  5038.9 1172.13  5059.9 1174.09
  5088.2 1177.75  5109.6 1179.45  5144.9 1183.91  5165.9  1185.5  5194.2 1188.98
  5222.6 1191.27  5229.9 1193.44  5265.1 1196.24  5293.4 1197.17  5300.5 1197.98
#Mann= 3 ,-1 , 0
  4267.8     .05       0  4995.3     .03       0  5003.7     .05       0
Bank Sta=4995.3,5003.7
XS Rating Curve= 0 ,0
Exp/Cntr=0.3,0.1

Type RM Length L Ch R = 1 ,7000    ,500,500,500
BEGIN DESCRIPTION:
HICKORY14 13.0
END DESCRIPTION:
XS GIS Cut Line= 3
      2742206.74     10227576.75      2741746.92     10227218.01
      2741441.48     10226927.84
#Sta/Elev= 30
  4416.8 1182.29  4483.8 1181.69  4711.7 1173.45  4761.5 1172.79  4790.4 1170.51
  4804.9 1170.16  4825.7 1171.64  4833.8 1173.43  4840.1 1172.69  4912.5 1173.08
  4947.8 1172.27  4962.2 1171.34  4968.6 1169.26  4976.2 1168.23  4995.7 1167.26
  4996.2 1166.76  5003.6 1166.76  5004.1 1167.26  5018.4 1170.52    5075 1173.98
  5131.6 1176.22  5167.2 1178.53  5174.1 1178.07  5216.6 1180.53  5251.8 1181.22
  5275.6 1182.48  5350.9  1183.9  5358.1 1184.84  5406.4 1185.75  5421.3 1186.22
#Mann= 5 ,-1 , 0
  4416.8     .05       0  4995.7     .03       0  5004.1     .05       0
  5275.6     .12       0  5406.4     .05       0
Bank Sta=4995.7,5004.1
XS Rating Curve= 0 ,0
Exp/Cntr=0.3,0.1

Type RM Length L Ch R = 1 ,6500    ,440,440,440
BEGIN DESCRIPTION:
HICKORY14 12.0
END DESCRIPTION:
XS GIS Cut Line= 4
      2742231.27     10227356.25      2742243.52     10226976.56
      2741995.46     10226878.27      2741496.35     10226774.46
#Sta/Elev= 30
  4353.3 1179.84  4406.5 1178.35  4493.6  1177.2  4594.1 1176.25  4696.6 1175.38
  4756.9  1176.1  4773.9 1176.97    4865 1176.21  4881.4 1175.59  4913.7 1172.06
    4919 1171.96  4924.5 1170.27  4943.4  1167.7  4948.7 1168.12  4967.5 1164.96
  4978.5 1166.65    5016 1164.91  5016.5 1164.41    5024 1164.41  5024.5 1164.91
  5030.4 1167.63  5040.6 1169.02  5091.7 1170.87  5132.6 1170.19  5173.4 1170.99
  5204.1 1170.37  5238.4 1171.72  5298.3 1173.08  5447.2 1179.27  5509.8    1183
#Mann= 7 ,-1 , 0
  4353.3     .05       0  4493.6     .12       0  4594.1     .05       0
    5016     .05       0  5024.5     .05       0  5238.4     .12       0
  5447.2     .05       0
Bank Sta=5016,5024.5
XS Rating Curve= 0 ,0
Exp/Cntr=0.3,0.1

Type RM Length L Ch R = 1 ,6060    ,477,477,477
BEGIN DESCRIPTION:
HICKORY14 11.0
END DESCRIPTION:
XS GIS Cut Line= 4
      2742261.89      10227276.7      2742268.02     10226860.19
        2741877.       10226519.      2741490.48     10226407.06
#Sta/Elev= 30
  4064.5 1176.59  4098.1 1178.35    4128 1177.17  4208.1 1175.83  4308.1  1174.7
  4523.6 1175.52  4615.7 1174.27  4685.9 1172.26  4693.5 1173.02  4700.1 1171.86
  4736.2 1170.64  4855.8 1169.37  4948.7 1165.34  4969.7  1167.6  4990.6 1164.68
  5007.5 1164.34    5008 1163.84  5016.1 1164.34  5032.6 1165.05  5038.5  1168.8
  5043.7 1167.91  5063.8 1170.77  5084.7 1170.01  5113.4 1171.74  5209.6 1175.53
  5250.4  1179.4  5255.6 1178.67  5289.2 1181.42  5314.3 1182.14  5402.4 1186.23
#Mann= 7 ,-1 , 0
  4064.5     .05       0    4128     .12       0  4208.1     .05       0
  5007.5     .05       0  5016.1     .05       0  5113.4     .12       0
  5314.3     .05       0
Bank Sta=5007.5,5016.1
XS Rating Curve= 0 ,0
Exp/Cntr=0.3,0.1

Type RM Length L Ch R = 1 ,5583    ,941,941,941
BEGIN DESCRIPTION:
HICKORY14 10.0
END DESCRIPTION:
XS GIS Cut Line= 3
      2742274.14      10227448.2      2742325.75       10226617.
      2742355.69     10226153.06
#Sta/Elev= 30
  4167.2 1180.31  4262.5 1178.87  4352.6 1175.96  4405.4 1176.46    4463 1175.03
    4543  1174.7  4603.1 1173.36  4733.4 1174.19  4813.5 1173.13  4863.6 1171.27
  4893.7 1169.14  4953.8 1167.46  4983.9 1164.63  4993.9 1163.46  4999.4  1161.6
  5009.6 1161.04  5010.1 1160.54  5018.2 1161.04    5034 1161.63    5044 1163.68
    5054 1164.51  5114.1 1167.79  5144.2 1170.22  5164.2 1170.46  5184.3 1173.49
  5235.7 1175.87  5304.5 1180.45  5314.5 1180.12  5374.7    1185  5464.9 1187.77
#Mann= 5 ,-1 , 0
  4167.2     .05       0  4405.4     .12       0    4463     .05       0
  5009.6     .05       0  5018.2     .05       0
Bank Sta=5009.6,5018.2
XS Rating Curve= 0 ,0
Exp/Cntr=0.3,0.1

Type RM Length L Ch R = 1 ,4642    ,783,783,783
BEGIN DESCRIPTION:
HICKORY14 9.0
END DESCRIPTION:
XS GIS Cut Line= 3
      2742405.68     10228003.13      2742708.75       10227293.
      2742776.36     10226143.59
#Sta/Elev= 30
  4227.9 1182.49  4347.8 1180.62    4478 1176.75  4532.4 1172.59  4600.2 1170.06
  4662.8 1172.01  4723.7  1170.5  4793.3 1170.51    4815 1168.72  4836.8 1169.53
  4876.2 1166.69  4928.9 1165.17  4952.5 1162.65  4984.6  1156.4  4985.1  1155.9
  4993.5  1156.4  5009.9 1158.04  5033.9 1163.21    5050 1164.41  5290.4 1165.14
  5320.4    1163  5374.5 1162.42  5380.5 1161.31  5430.6 1162.26  5580.9 1168.47
  5654.4  1168.6  5674.5  1168.9  5731.2  1169.6  5941.5 1177.01  6151.4 1181.22
#Mann= 5 ,-1 , 0
  4227.9     .05       0  4984.6     .05       0  4993.5     .05       0
  5654.4     .12       0  5674.5     .05       0
Bank Sta=4984.6,4993.5
XS Rating Curve= 0 ,0
Exp/Cntr=0.3,0.1

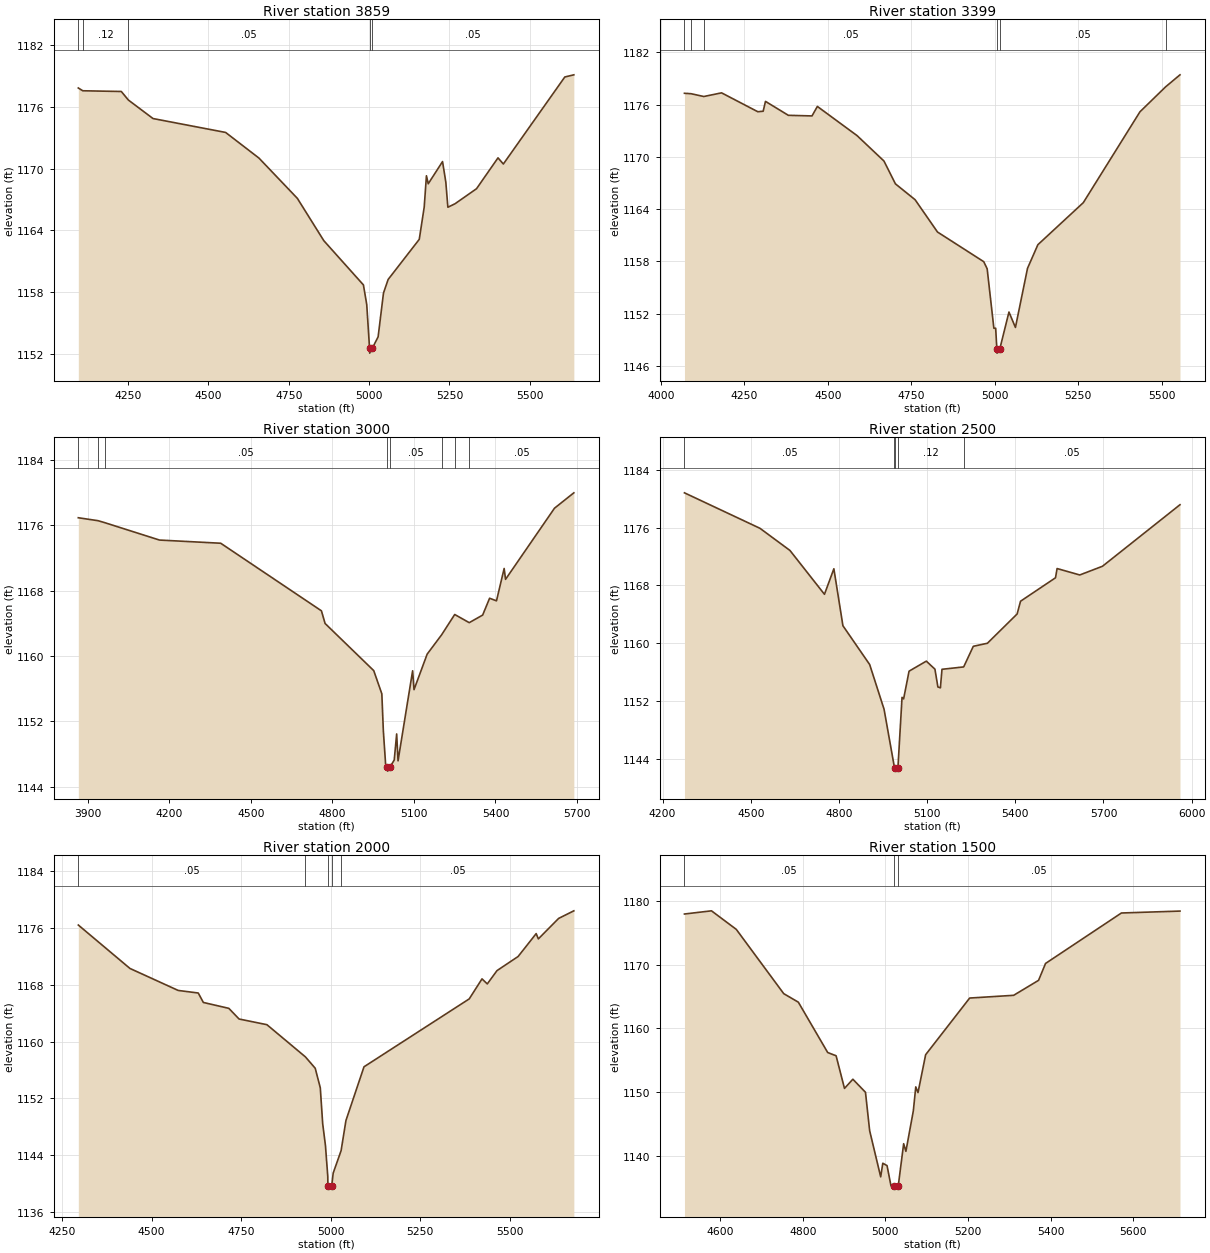
Type RM Length L Ch R = 1 ,3859    ,460,460,460
BEGIN DESCRIPTION:
HICKORY14 8.0
END DESCRIPTION:
XS GIS Cut Line= 4
      2743045.84     10227589.02      2743233.14     10227166.57
        2743132.       10226736.      2742843.71     10226168.08
#Sta/Elev= 30
  4095.6 1177.83  4109.5 1177.56  4229.4 1177.49  4251.3 1176.66    4328 1174.86
  4553.8 1173.51  4657.4 1171.02    4777  1167.1  4859.2 1162.99  4982.4 1158.69
  4992.7 1156.79  5001.4 1152.56  5001.9 1152.06  5010.4 1152.56  5028.1 1153.64
  5044.8  1157.9  5059.3 1159.22  5156.1 1163.12  5171.5 1166.26  5178.4  1169.3
    5184 1168.52  5228.5 1170.68  5238.7 1168.68  5245.1 1166.24  5267.4 1166.58
  5334.2 1168.04    5401 1171.04  5417.6 1170.44  5608.8  1178.9  5636.9 1179.11
#Mann= 5 ,-1 , 0
  4095.6     .05       0  4109.5     .12       0  4251.3     .05       0
  5001.4     .05       0  5010.4     .05       0
Bank Sta=5001.4,5010.4
XS Rating Curve= 0 ,0
Exp/Cntr=0.3,0.1

Type RM Length L Ch R = 1 ,3399    ,399,399,399
BEGIN DESCRIPTION:
HICKORY14 7.0
END DESCRIPTION:
XS GIS Cut Line= 3
      2743076.47     10227595.13        2743529.       10226783.
      2743713.43     10226259.96
#Sta/Elev= 30
  4070.3 1177.31  4090.1 1177.26  4128.3 1176.94  4181.5 1177.36  4290.1 1175.19
  4306.1 1175.25    4313 1176.38  4381.5 1174.78  4452.4 1174.71  4468.4  1175.8
  4587.3 1172.45  4667.9 1169.53  4702.2 1166.91  4761.1 1165.09  4828.2 1161.38
  4966.8 1157.97    4977 1157.16  4997.1 1150.33  5002.5 1150.33    5006 1147.97
  5006.5 1147.47    5015 1147.97  5042.3 1152.19  5061.7 1150.42  5097.9 1157.21
  5128.9 1159.92    5265 1164.75  5434.6 1175.18  5511.5 1178.05  5554.6 1179.43
#Mann= 6 ,-1 , 0
  4070.3     .05       0  4090.1     .12       0  4128.3     .05       0
    5006     .03       0    5015     .05       0  5511.5     .12       0
Bank Sta=5006,5015
XS Rating Curve= 0 ,0
Exp/Cntr=0.3,0.1

Type RM Length L Ch R = 1 ,3000    ,500,500,500
BEGIN DESCRIPTION:
HICKORY14 6.0
END DESCRIPTION:
XS GIS Cut Line= 4
      2743064.21     10227662.53      2743339.82     10227215.42
      2743877.87     10226930.41      2743755.69     10226253.14
#Sta/Elev= 30
  3865.9 1176.91  3938.3 1176.55  3963.9  1176.3  4164.4 1174.18  4389.6 1173.79
  4759.9 1165.52  4773.4 1163.97  4952.3  1158.2  4982.1 1155.36  4987.7 1150.79
  4995.9 1146.78  5002.9  1146.4  5003.4  1145.9    5012  1146.4  5027.7 1147.26
  5036.6 1150.45  5041.7 1147.16  5095.3 1158.18  5100.4 1155.87  5148.8 1160.22
  5202.1 1162.59  5250.1 1165.07  5303.5 1164.07  5352.9    1165  5378.4 1167.06
  5403.7 1166.74  5431.9  1170.7    5437 1169.37  5617.1 1178.08  5688.2 1179.96
#Mann= 8 ,-1 , 0
  3865.9     .05       0  3938.3     .12       0  3963.9     .05       0
  5002.9     .05       0    5012     .05       0  5202.1     .05       0
  5250.1     .12       0  5303.5     .05       0
Bank Sta=5002.9,5012
XS Rating Curve= 0 ,0
Exp/Cntr=0.3,0.1

Type RM Length L Ch R = 1 ,2500    ,500,500,500
BEGIN DESCRIPTION:
HICKORY14 5.0
END DESCRIPTION:
XS GIS Cut Line= 3
      2744430.01     10227809.52      2744177.19      10227129.6
      2743811.41     10226241.58
#Sta/Elev= 30
  4274.6 1180.84  4531.5 1175.92  4633.5 1172.85  4750.9 1166.77  4782.9 1170.31
  4813.7 1162.41  4904.7 1157.03  4953.6 1150.84  4988.2 1142.93  4990.1 1142.75
  4990.6 1142.25  5000.9 1142.75  5014.8 1152.48  5020.2 1152.27  5038.7 1156.11
  5097.4  1157.5  5126.7 1156.39  5136.8 1153.92  5145.3  1153.8  5150.7 1156.37
  5224.5  1156.7  5257.3 1159.56  5305.2 1159.98  5406.3 1164.04    5418 1165.81
  5536.9 1169.06  5542.3 1170.34  5619.5 1169.45  5696.8 1170.66  5960.4 1179.19
#Mann= 5 ,-1 , 0
  4274.6     .05       0  4988.2     .12       0  4990.1     .07       0
  5000.9     .12       0  5224.5     .05       0
Bank Sta=4990.1,5000.9
XS Rating Curve= 0 ,0
Exp/Cntr=0.3,0.1

Type RM Length L Ch R = 1 ,2000    ,500,500,500
BEGIN DESCRIPTION:
HICKORY14 4.0
END DESCRIPTION:
XS GIS Cut Line= 3
      2744797.47     10227264.41       2744266.9     10226800.63
      2743872.81     10226247.94
#Sta/Elev= 30
  4295.3 1176.42  4439.4 1170.31  4574.2 1167.21  4630.2 1166.85  4644.4 1165.52
  4715.6 1164.69  4744.1 1163.19  4821.9 1162.39  4929.3 1157.86  4956.7 1156.26
  4970.9  1153.5  4977.6 1148.44  4985.2 1145.42  4991.8 1141.04  4992.1 1139.74
  4992.6 1139.24  5002.9 1139.74  5006.9  1141.5    5029 1144.66  5042.5  1148.9
  5092.9 1156.46  5386.7 1166.02  5422.4 1168.84  5437.1 1168.13  5464.2    1170
  5523.2 1171.99  5573.6 1175.21  5579.7 1174.47  5636.3 1177.35  5678.8 1178.42
#Mann= 5 ,-1 , 0
  4295.3     .05       0  4929.3     .12       0  4992.1     .07       0
  5002.9     .12       0    5029     .05       0
Bank Sta=4992.1,5002.9
XS Rating Curve= 0 ,0
Exp/Cntr=0.3,0.1

Type RM Length L Ch R = 1 ,1500    ,500,500,500
BEGIN DESCRIPTION:
HICKORY14 3.0
END DESCRIPTION:
XS GIS Cut Line= 3
      2744987.31     10226498.84      2744508.24     10226416.43
       2743849.4     10226144.12
#Sta/Elev= 30
  4513.9 1177.96  4579.3 1178.46  4639.3 1175.55  4754.1 1165.46  4789.5 1164.12
  4860.5 1156.22  4880.8 1155.71  4901.1 1150.59  4921.4 1152.03  4951.9 1149.98
    4962 1143.95  4988.7 1136.71  4993.8 1138.84  5004.1 1138.47  5013.6  1135.3
  5020.4 1135.28  5020.9 1134.78  5031.2 1135.28  5044.3 1141.91  5049.7 1140.71
  5067.7 1147.07  5073.6 1150.83    5079 1149.93  5097.5 1155.88    5204 1164.77
  5310.5  1165.2  5370.7 1167.55  5387.6  1170.2  5571.2 1178.12  5712.9 1178.42
#Mann= 3 ,-1 , 0
  4513.9     .05       0  5020.4     .05       0  5031.2     .05       0
Bank Sta=5020.4,5031.2
XS Rating Curve= 0 ,0
Exp/Cntr=0.3,0.1

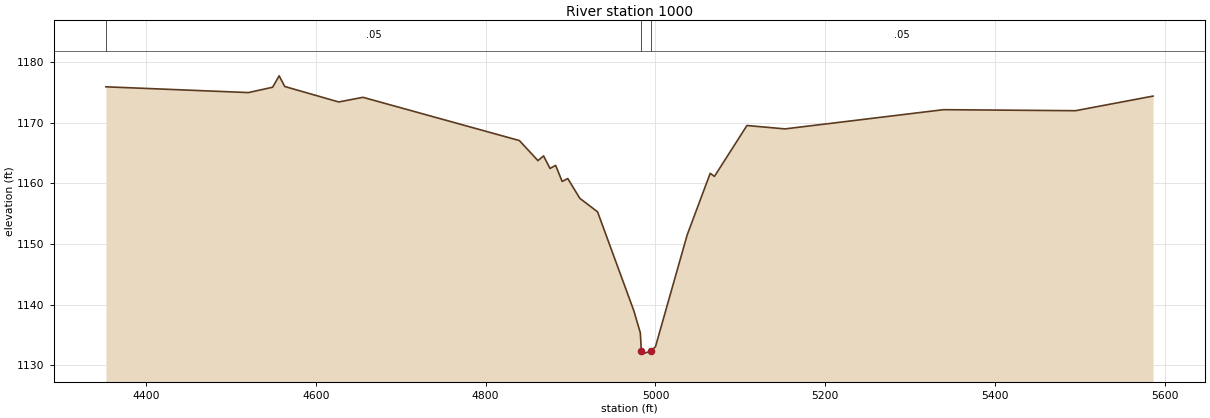
Type RM Length L Ch R = 1 ,1000    ,0,0,0
BEGIN DESCRIPTION:
HICKORY14 2.0
END DESCRIPTION:
XS GIS Cut Line= 3
       2744932.2     10226364.08      2744442.75     10225940.34
      2743860.56     10226008.86
#Sta/Elev= 30
  4352.6 1175.91  4520.5 1174.96    4549 1175.84  4556.7 1177.72  4563.3 1175.96
  4626.9 1173.41  4655.4 1174.18  4839.7 1167.05  4861.6 1163.74  4868.2 1164.52
  4875.8 1162.45  4882.4 1162.96  4890.1 1160.31  4896.7 1160.79  4910.9 1157.53
  4931.8  1155.3  4974.6 1138.97  4982.2 1135.35  4983.4 1132.34  4983.9 1131.84
  4994.3 1132.34    5000 1133.05  5037.3 1151.46  5064.5 1161.65  5069.5 1161.14
  5107.8 1169.53  5152.6 1168.97  5339.4 1172.14  5494.9 1171.97  5586.2 1174.38
#Mann= 3 ,-1 , 0
  4352.6     .05       0  4983.4     .05       0  4994.3     .05       0
Bank Sta=4983.4,4994.3
XS Rating Curve= 0 ,0
Exp/Cntr=0.3,0.1

Chan Stop Cuts=-1
Use User Specified Reach Order=0
Composite Channel Slope=5