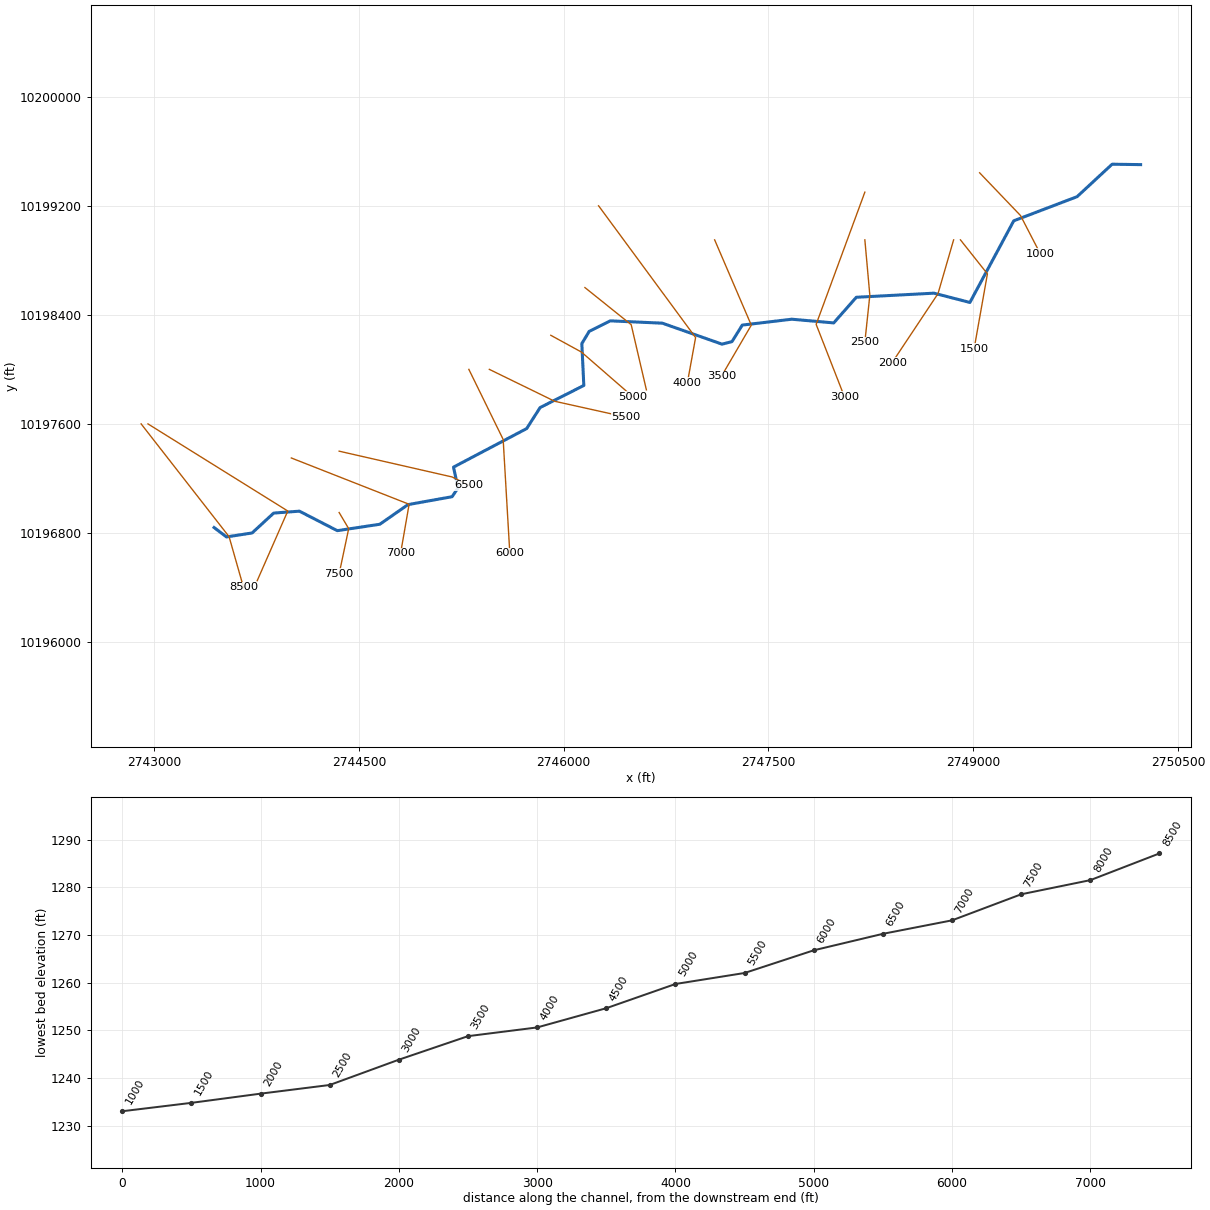
--- HICKORY15.prj (project) ---

Proj Title=HICKORY15 Base Level Engineering
Current Plan=p01
Default Exp/Contr=0.3,0.1
English Units
Geom File=g01
Flow File=f01
Plan File=p01
BEGIN DESCRIPTION:
HICKORY15
END DESCRIPTION:

--- HICKORY15.p01 (plan) ---

Plan Title=Multiple Run
Short Identifier=Multiple
Geom File=g01
Flow File=f01
Subcritical Flow
K Sum by GR= 0
Std Step Tol= 0.01
Critical Tol= 0.01
Num of Std Step Trials= 20
Max Error Tol= 0.3
Flow Tol Ratio= 0.001
Split Flow NTrial= 30
Split Flow Tol= 0.02
Split Flow Ratio= 0.02
Log Output Level= 0
Friction Slope Method= 1
Unsteady Friction Slope Method= 2
Unsteady Bridges Friction Slope Method= 1
Parabolic Critical Depth
Global Vel Dist=  1 , 1 , 1
Global Log Level= 0
CheckData=True
Encroach Param= -1, 0, 0, 0
BEGIN DESCRIPTION:
Multiple Run
END DESCRIPTION:

--- HICKORY15.f01 (steady flow) ---

Flow Title=Multiple
Number of Profiles=7
Profile Names=10-year,25-year,50-year,1pct_min,100-year,1pct_plu,500-year
River Rch & RM= HICKORY15,Reach-1,8500
     470     766     903     651    1188    2169    1608
River Rch & RM= HICKORY15,Reach-1,5000
     610    1003    1310     984    1746    3099    2355
Boundary for River Rch & Prof#=HICKORY15,Reach-1,1
Up Type=0
Dn Type=3
Dn Slope=0.005
Boundary for River Rch & Prof#=HICKORY15,Reach-1,2
Up Type=0
Dn Type=3
Dn Slope=0.005
Boundary for River Rch & Prof#=HICKORY15,Reach-1,3
Up Type=0
Dn Type=3
Dn Slope=0.005
Boundary for River Rch & Prof#=HICKORY15,Reach-1,4
Up Type=0
Dn Type=3
Dn Slope=0.005
Boundary for River Rch & Prof#=HICKORY15,Reach-1,5
Up Type=0
Dn Type=3
Dn Slope=0.005
Boundary for River Rch & Prof#=HICKORY15,Reach-1,6
Up Type=0
Dn Type=3
Dn Slope=0.005
Boundary for River Rch & Prof#=HICKORY15,Reach-1,7
Up Type=0
Dn Type=3
Dn Slope=0.005

--- HICKORY15.g01 (geometry) ---

Geom Title=Existing Conditions

River Reach=HICKORY15,Reach-1
Reach XY= 30
      2743439.75     10196843.00      2743530.50     10196774.00
      2743718.25     10196803.00      2743876.50     10196949.00
      2744064.50     10196963.00      2744342.25     10196820.00
      2744653.75     10196867.00      2744860.00     10197011.00
      2745183.00     10197069.00      2745226.25     10197134.00
      2745193.25     10197286.00      2745729.25     10197569.00
      2745827.50     10197723.00      2746147.50     10197885.00
      2746133.00     10198192.00      2746187.00     10198282.00
      2746341.25     10198359.00      2746722.50     10198342.00
      2747160.00     10198188.00      2747233.00     10198207.00
      2747308.00     10198328.00      2747670.50     10198371.00
      2747977.75     10198344.00      2748143.25     10198532.00
      2748711.50     10198562.00      2748975.00     10198494.00
      2749296.25     10199093.00      2749760.00     10199270.00
      2750016.50     10199508.00      2750225.25     10199505.00

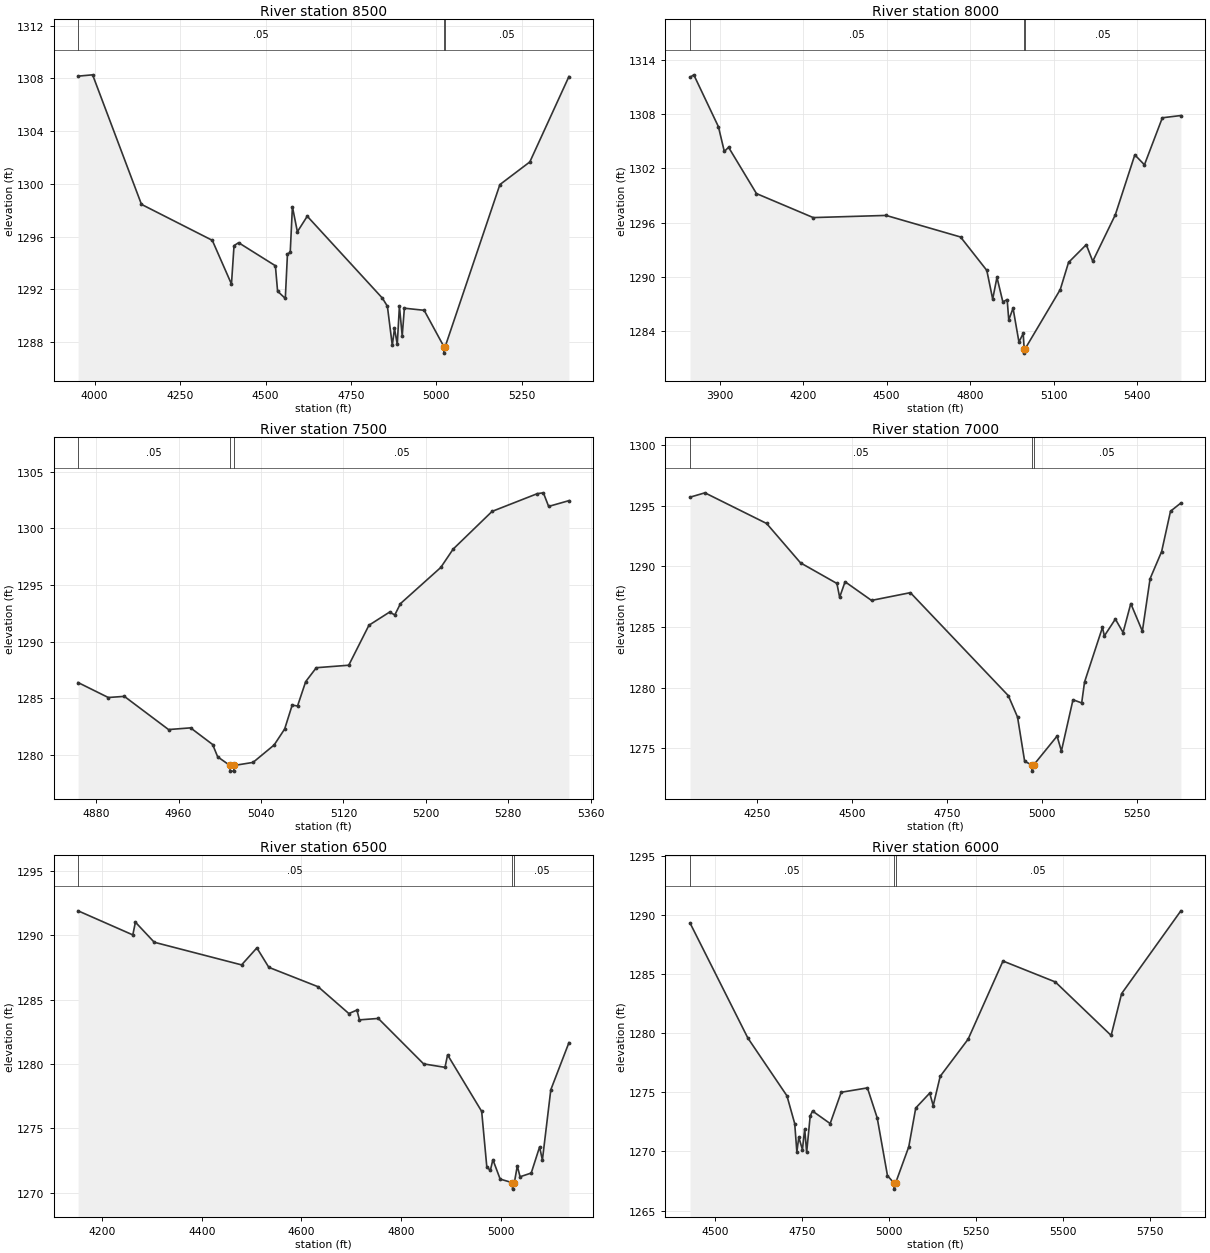
Type RM Length L Ch R = 1,8500,500,500,500
BEGIN DESCRIPTION:
HICKORY15 17.0
END DESCRIPTION:
XS GIS Cut Line= 3
      2742905.71     10197603.08      2743549.71     10196775.92
      2743655.69     10196403.09
#Sta/Elev= 30
  3951.7 1308.17  3994.2 1308.27  4137.1 1298.44  4344.3 1295.71  4400.4 1292.39
  4407.9 1295.31  4421.3 1295.53  4528.9 1293.78  4535.3 1291.85  4557.9 1291.30
  4564.2 1294.67  4572.3 1294.80  4578.7 1298.26  4593.2 1296.36  4622.1 1297.54
  4842.0 1291.32  4856.5 1290.71  4870.9 1287.74  4877.3 1289.02  4885.4 1287.82
  4891.7 1290.71  4899.9 1288.46  4906.2 1290.56  4964.1 1290.40  5021.7 1287.65
  5022.0 1287.15  5025.7 1287.65  5185.6 1299.94  5273.2 1301.66  5387.6 1308.14
#Mann=3,-1,0
  3951.7    0.05       0  5021.7    0.05       0  5025.7    0.05       0
Bank Sta=5021.7,5025.7
Exp/Cntr=0.3,0.1

Type RM Length L Ch R = 1,8000,500,500,500
BEGIN DESCRIPTION:
HICKORY15 16.0
END DESCRIPTION:
XS GIS Cut Line= 3
      2742955.66     10197603.13      2743979.55     10196964.18
      2743755.70     10196453.16
#Sta/Elev= 30
  3793.1 1312.11  3806.7 1312.38  3895.2 1306.63  3916.4 1303.89  3931.7 1304.35
  4032.0 1299.22  4236.1 1296.56  4498.0 1296.80  4765.7 1294.41  4860.1 1290.71
  4881.3 1287.53  4896.7 1289.94  4917.9 1287.21  4933.3 1287.48  4939.1 1285.21
  4954.5 1286.52  4975.7 1282.77  4991.1 1283.73  4994.3 1282.04  4994.5 1281.54
  4998.3 1282.04  5124.3 1288.59  5154.0 1291.59  5217.8 1293.56  5241.1 1291.72
  5322.2 1296.87  5392.3 1303.51  5426.9 1302.41  5491.3 1307.62  5557.9 1307.87
#Mann=3,-1,0
  3793.1    0.05       0  4994.3    0.03       0  4998.3    0.05       0
Bank Sta=4994.3,4998.3
Exp/Cntr=0.3,0.1

Type RM Length L Ch R = 1,7500,500,500,500
BEGIN DESCRIPTION:
HICKORY15 15.0
END DESCRIPTION:
XS GIS Cut Line= 3
      2744355.69     10196953.11      2744425.67     10196834.75
      2744355.69     10196503.15
#Sta/Elev= 30
  4862.5 1286.39  4891.8 1285.07  4907.4 1285.17  4950.3 1282.24  4971.7 1282.39
  4993.1 1280.92  4998.0 1279.83  5009.9 1279.07  5010.1 1278.57  5013.6 1278.57
  5013.9 1279.07  5032.3 1279.34  5052.8 1280.88  5063.0 1282.29  5070.3 1284.40
  5075.5 1284.32  5083.4 1286.47  5093.7 1287.70  5125.2 1287.92  5144.8 1291.45
  5164.8 1292.61  5169.9 1292.36  5175.4 1293.36  5214.5 1296.55  5226.5 1298.17
  5264.3 1301.50  5308.3 1303.07  5314.1 1303.14  5319.2 1301.94  5338.9 1302.45
#Mann=3,-1,0
  4862.5    0.05       0  5009.9    0.05       0  5013.9    0.05       0
Bank Sta=5009.9,5013.9
Exp/Cntr=0.3,0.1

Type RM Length L Ch R = 1,7000,500,500,500
BEGIN DESCRIPTION:
HICKORY15 14.0
END DESCRIPTION:
XS GIS Cut Line= 3
      2744005.73     10197353.09      2744868.11     10197013.60
      2744805.69     10196653.16
#Sta/Elev= 30
  4073.2 1295.71  4112.4 1296.07  4274.9 1293.54  4364.2 1290.29  4460.0 1288.59
  4467.2 1287.45  4481.5 1288.73  4551.1 1287.19  4653.5 1287.83  4911.4 1279.33
  4935.7 1277.56  4954.4 1273.91  4973.9 1273.60  4974.1 1273.10  4977.9 1273.60
  5039.8 1275.99  5051.2 1274.76  5081.7 1278.99  5104.6 1278.73  5112.1 1280.45
  5159.3 1284.96  5164.3 1284.26  5193.3 1285.65  5213.6 1284.54  5233.9 1286.93
  5264.4 1284.65  5284.7 1288.98  5315.1 1291.22  5338.5 1294.55  5365.8 1295.23
#Mann=3,-1,0
  4073.2    0.05       0  4973.9    0.03       0  4977.9    0.05       0
Bank Sta=4973.9,4977.9
Exp/Cntr=0.3,0.1

Type RM Length L Ch R = 1,6500,500,500,500
BEGIN DESCRIPTION:
HICKORY15 13.0
END DESCRIPTION:
XS GIS Cut Line= 3
      2744355.68     10197403.11      2745182.92     10197213.91
      2745305.69     10197153.11
#Sta/Elev= 30
  4151.4 1291.89  4261.3 1290.02  4266.5 1291.01  4304.3 1289.45  4479.7 1287.69
  4510.4 1289.01  4534.4 1287.50  4633.5 1285.99  4695.1 1283.91  4711.3 1284.18
  4716.4 1283.42  4754.2 1283.53  4845.2 1280.00  4888.2 1279.73  4893.3 1280.70
  4961.8 1276.31  4972.1 1272.00  4979.2 1271.72  4984.3 1272.56  4998.9 1271.05
  5023.4 1270.77  5023.7 1270.27  5027.4 1270.77  5033.3 1272.07  5038.9 1271.23
  5061.3 1271.52  5078.1 1273.55  5083.7 1272.53  5100.6 1277.99  5137.0 1281.65
#Mann=3,-1,0
  4151.4    0.05       0  5023.4    0.03       0  5027.4    0.05       0
Bank Sta=5023.4,5027.4
Exp/Cntr=0.3,0.1

Type RM Length L Ch R = 1,6000,500,500,500
BEGIN DESCRIPTION:
HICKORY15 12.0
END DESCRIPTION:
XS GIS Cut Line= 3
      2745305.68     10198003.13      2745556.83     10197489.33
      2745605.68     10196653.15
#Sta/Elev= 30
  4428.1 1289.34  4594.2 1279.60  4706.4 1274.71  4728.7 1272.36  4734.9 1269.96
  4740.4 1271.20  4750.9 1270.16  4757.4 1271.91  4763.0 1269.93  4773.2 1273.01
  4779.9 1273.42  4830.5 1272.36  4862.2 1275.01  4937.5 1275.38  4965.6 1272.84
  4995.1 1267.95  5014.2 1267.31  5014.5 1266.81  5018.2 1267.31  5056.3 1270.40
  5076.3 1273.68  5116.4 1274.94  5126.4 1273.88  5146.5 1276.36  5226.6 1279.50
  5326.8 1286.12  5477.0 1284.35  5637.3 1279.82  5667.4 1283.36  5837.6 1290.37
#Mann=3,-1,0
  4428.1    0.05       0  5014.2    0.05       0  5018.2    0.05       0
Bank Sta=5014.2,5018.2
Exp/Cntr=0.3,0.1

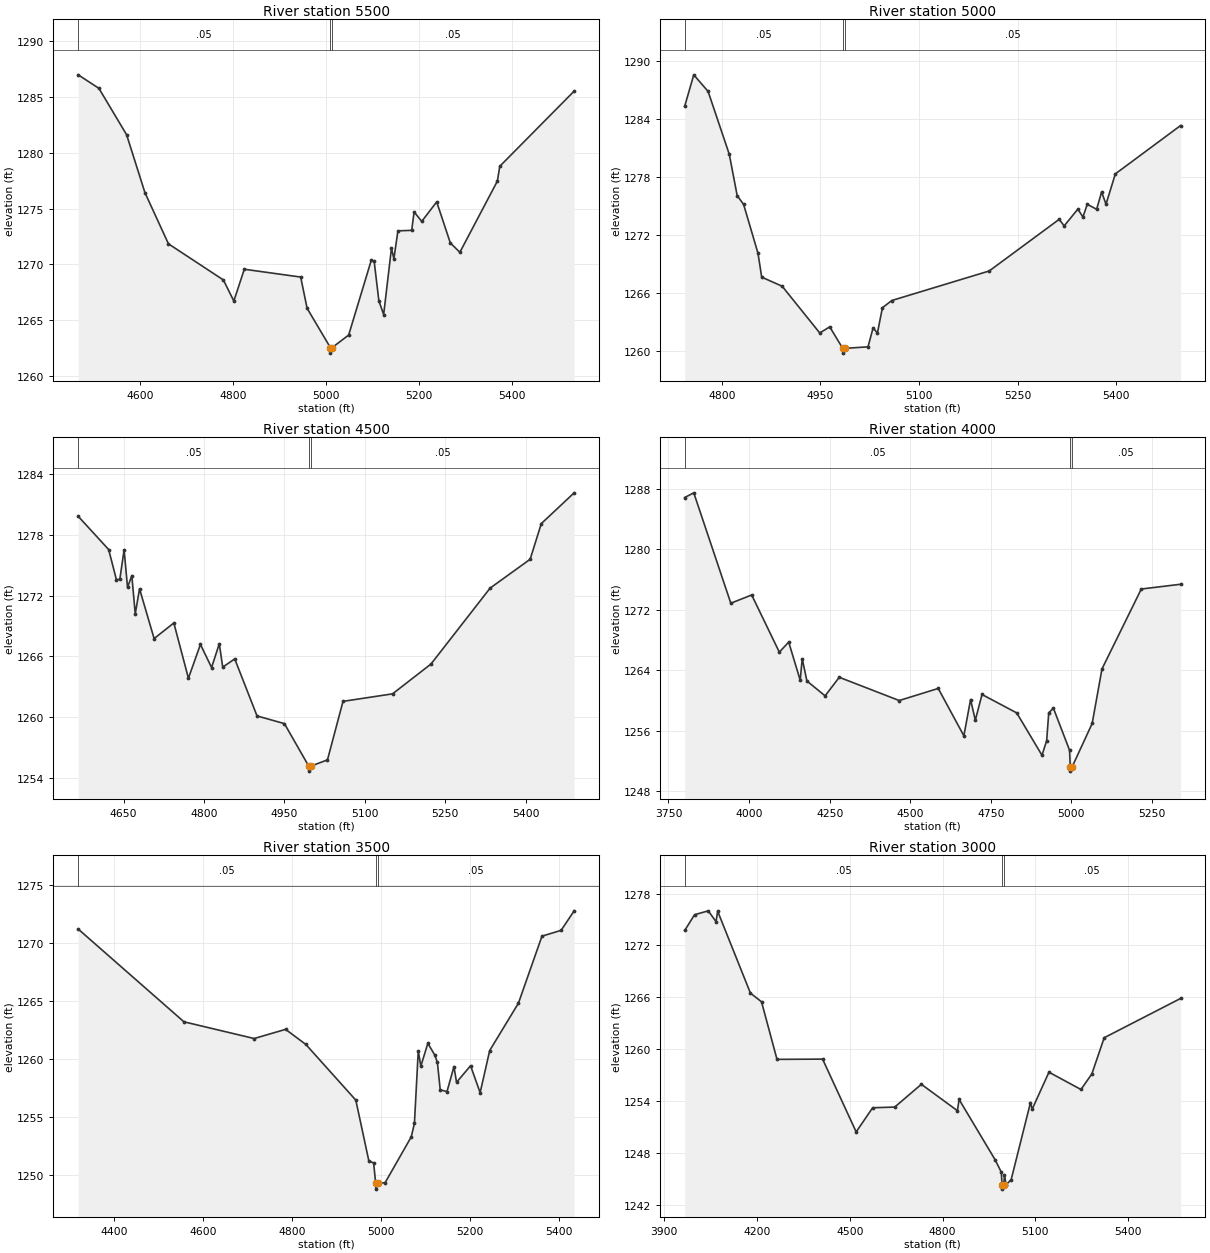
Type RM Length L Ch R = 1,5500,500,500,500
BEGIN DESCRIPTION:
HICKORY15 11.0
END DESCRIPTION:
XS GIS Cut Line= 3
      2745455.72     10198003.10      2745934.28     10197769.11
      2746455.73     10197653.10
#Sta/Elev= 30
  4467.3 1287.00  4511.8 1285.79  4571.4 1281.63  4610.8 1276.44  4661.4 1271.85
  4779.6 1268.61  4802.1 1266.72  4824.6 1269.57  4945.9 1268.87  4959.7 1266.07
  5009.7 1262.55  5009.9 1262.05  5013.7 1262.55  5049.1 1263.67  5097.7 1270.37
  5103.9 1270.31  5114.1 1266.74  5124.4 1265.51  5141.2 1271.46  5146.4 1270.51
  5155.1 1273.01  5184.7 1273.06  5189.9 1274.71  5206.3 1273.86  5238.5 1275.61
  5267.8 1271.93  5288.3 1271.09  5369.0 1277.47  5374.2 1278.80  5534.2 1285.54
#Mann=3,-1,0
  4467.3    0.05       0  5009.7    0.05       0  5013.7    0.05       0
Bank Sta=5009.7,5013.7
Exp/Cntr=0.3,0.1

Type RM Length L Ch R = 1,5000,500,500,500
BEGIN DESCRIPTION:
HICKORY15 10.0
END DESCRIPTION:
XS GIS Cut Line= 3
      2745905.68     10198253.12      2746130.45     10198129.97
      2746505.66     10197803.13
#Sta/Elev= 30
  4743.7 1285.31  4757.5 1288.57  4779.3 1286.85  4811.5 1280.34  4823.5 1276.06
  4833.3 1275.14  4855.1 1270.10  4860.8 1267.61  4891.9 1266.67  4949.0 1261.83
  4964.2 1262.46  4983.9 1260.24  4984.1 1259.74  4988.1 1260.24  5022.4 1260.39
  5030.1 1262.35  5036.7 1261.83  5044.3 1264.44  5058.5 1265.19  5206.6 1268.25
  5313.0 1273.60  5320.6 1272.92  5341.4 1274.66  5349.1 1273.84  5355.7 1275.16
  5369.9 1274.64  5377.5 1276.43  5384.2 1275.17  5398.4 1278.31  5497.6 1283.32
#Mann=3,-1,0
  4743.7    0.05       0  4983.9    0.05       0  4988.1    0.05       0
Bank Sta=4983.9,4988.1
Exp/Cntr=0.3,0.1

Type RM Length L Ch R = 1,4500,500,500,500
BEGIN DESCRIPTION:
HICKORY15 9.0
END DESCRIPTION:
XS GIS Cut Line= 3
      2746155.71     10198603.09      2746494.50     10198331.04
      2746605.69     10197853.10
#Sta/Elev= 30
  4565.5 1279.82  4622.3 1276.54  4636.7 1273.58  4643.1 1273.59  4651.1 1276.51
  4657.5 1272.81  4665.5 1273.96  4671.9 1270.19  4679.9 1272.66  4707.1 1267.75
  4743.9 1269.29  4771.1 1263.83  4793.5 1267.17  4814.3 1264.89  4828.7 1267.24
  4835.1 1264.93  4857.5 1265.74  4899.1 1260.11  4950.2 1259.35  4995.5 1255.16
  4995.7 1254.66  4999.7 1255.16  5030.5 1255.77  5059.5 1261.55  5151.9 1262.29
  5223.7 1265.24  5333.9 1272.73  5408.6 1275.58  5429.4 1279.10  5490.7 1282.14
#Mann=3,-1,0
  4565.5    0.05       0  4995.5    0.03       0  4999.7    0.05       0
Bank Sta=4995.5,4999.7
Exp/Cntr=0.3,0.1

Type RM Length L Ch R = 1,4000,500,500,500
BEGIN DESCRIPTION:
HICKORY15 8.0
END DESCRIPTION:
XS GIS Cut Line= 3
      2746255.68     10199203.11      2746966.19     10198236.44
      2746905.68     10197903.09
#Sta/Elev= 30
  3800.3 1286.86  3828.5 1287.48  3943.4 1272.86  4008.2 1273.95  4093.9 1266.38
  4123.0 1267.71  4158.7 1262.65  4164.9 1265.51  4179.5 1262.56  4235.9 1260.59
  4279.8 1263.05  4465.8 1259.97  4586.9 1261.57  4666.4 1255.30  4687.2 1260.10
  4701.9 1257.36  4722.7 1260.77  4830.4 1258.33  4908.7 1252.72  4923.3 1254.67
  4929.7 1258.35  4944.2 1258.96  4994.3 1253.38  4996.4 1251.12  4996.8 1250.62
  5001.6 1251.12  5064.4 1256.93  5094.9 1264.16  5216.8 1274.74  5338.8 1275.37
#Mann=3,-1,0
  3800.3    0.05       0  4996.4    0.05       0  5001.6    0.05       0
Bank Sta=4996.4,5001.6
Exp/Cntr=0.3,0.1

Type RM Length L Ch R = 1,3500,500,500,500
BEGIN DESCRIPTION:
HICKORY15 7.0
END DESCRIPTION:
XS GIS Cut Line= 3
      2747105.68     10198953.12      2747374.02     10198327.44
      2747155.71     10197953.15
#Sta/Elev= 30
  4319.2 1271.17  4556.7 1263.19  4714.4 1261.75  4785.1 1262.54  4830.6 1261.24
  4942.8 1256.45  4972.1 1251.22  4982.9 1251.04  4987.4 1249.29  4987.8 1248.79
  4992.6 1249.29  5008.7 1249.35  5067.4 1253.29  5074.5 1254.45  5083.1 1260.69
  5088.9 1259.37  5104.6 1261.34  5120.3 1260.32  5126.1 1259.69  5132.4 1257.34
  5147.6 1257.18  5163.3 1259.33  5169.1 1257.98  5200.6 1259.41  5222.1 1257.09
  5243.6 1260.72  5308.1 1264.79  5361.0 1270.56  5404.0 1271.06  5433.3 1272.74
#Mann=3,-1,0
  4319.2    0.05       0  4987.4    0.03       0  4992.6    0.05       0
Bank Sta=4987.4,4992.6
Exp/Cntr=0.3,0.1

Type RM Length L Ch R = 1,3000,500,500,500
BEGIN DESCRIPTION:
HICKORY15 6.0
END DESCRIPTION:
XS GIS Cut Line= 3
      2748205.68     10199303.10      2747848.97     10198333.33
      2748055.69     10197803.10
#Sta/Elev= 30
  3966.7 1273.73  3998.7 1275.55  4042.9 1276.00  4068.0 1274.75  4073.3 1275.95
  4179.2 1266.49  4215.0 1265.49  4265.0 1258.84  4412.3 1258.87  4520.8 1250.46
  4574.0 1253.25  4645.4 1253.33  4731.4 1255.96  4848.0 1252.91  4853.3 1254.21
  4969.8 1247.24  4989.6 1245.82  4992.2 1244.35  4992.7 1243.85  4997.7 1244.35
  5000.0 1245.50  5005.2 1244.35  5021.7 1244.96  5084.0 1253.85  5089.4 1253.08
  5143.7 1257.36  5247.1 1255.36  5282.3 1257.16  5322.2 1261.34  5569.1 1265.88
#Mann=3,-1,0
  3966.7    0.05       0  4992.2    0.03       0  4997.7    0.05       0
Bank Sta=4992.2,4997.7
Exp/Cntr=0.3,0.1

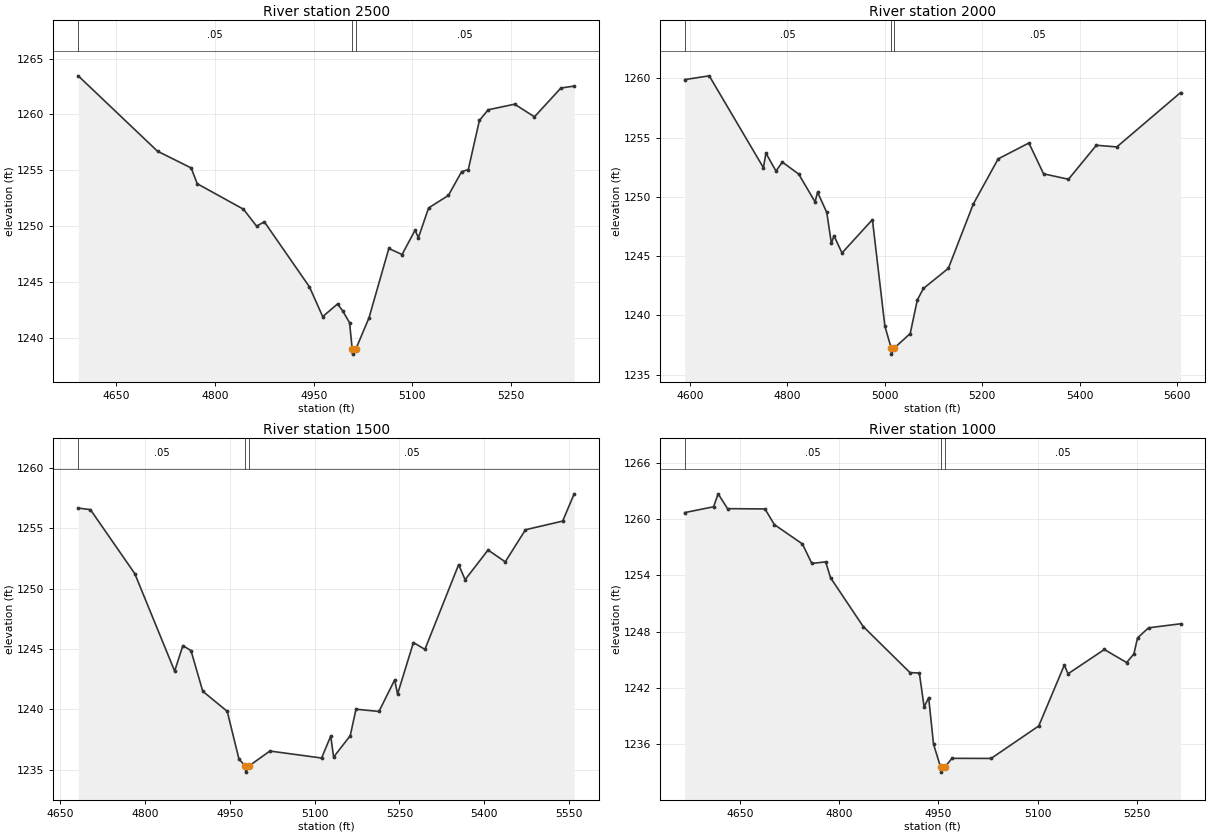
Type RM Length L Ch R = 1,2500,500,500,500
BEGIN DESCRIPTION:
HICKORY15 5.0
END DESCRIPTION:
XS GIS Cut Line= 3
      2748205.68     10198953.14      2748242.16     10198546.97
      2748205.68     10198203.10
#Sta/Elev= 30
  4592.2 1263.46  4712.7 1256.71  4763.9 1255.21  4773.0 1253.80  4843.2 1251.52
  4863.3 1250.00  4875.0 1250.39  4943.6 1244.56  4963.7 1241.90  4986.2 1243.03
  4993.8 1242.44  5004.5 1241.36  5008.5 1239.04  5009.0 1238.54  5014.4 1239.04
  5034.1 1241.80  5064.2 1248.00  5084.3 1247.46  5104.1 1249.64  5109.1 1248.96
  5124.6 1251.63  5154.7 1252.75  5174.8 1254.88  5184.9 1255.06  5201.8 1259.46
  5215.1 1260.42  5255.3 1260.92  5285.5 1259.79  5325.7 1262.37  5345.8 1262.54
#Mann=3,-1,0
  4592.2    0.05       0  5008.5    0.03       0  5014.4    0.05       0
Bank Sta=5008.5,5014.4
Exp/Cntr=0.3,0.1

Type RM Length L Ch R = 1,2000,500,500,500
BEGIN DESCRIPTION:
HICKORY15 4.0
END DESCRIPTION:
XS GIS Cut Line= 3
      2748855.69     10198953.12      2748741.37     10198558.55
      2748405.66     10198053.07
#Sta/Elev= 30
  4589.2 1259.89  4639.6 1260.21  4750.7 1252.46  4756.0 1253.68  4776.6 1252.17
  4789.5 1252.93  4823.1 1251.92  4856.7 1249.57  4861.9 1250.39  4880.7 1248.68
  4890.3 1246.06  4895.5 1246.72  4912.0 1245.26  4974.4 1248.07  5000.0 1239.08
  5013.0 1237.22  5013.5 1236.72  5018.9 1237.22  5052.0 1238.46  5066.5 1241.29
  5079.0 1242.26  5130.2 1243.96  5181.3 1249.38  5232.4 1253.20  5295.5 1254.54
  5325.6 1251.94  5376.7 1251.48  5433.9 1254.35  5475.9 1254.21  5606.8 1258.80
#Mann=3,-1,0
  4589.2    0.05       0  5013.0    0.05       0  5018.9    0.05       0
Bank Sta=5013,5018.9
Exp/Cntr=0.3,0.1

Type RM Length L Ch R = 1,1500,500,500,500
BEGIN DESCRIPTION:
HICKORY15 3.0
END DESCRIPTION:
XS GIS Cut Line= 3
      2748905.71     10198953.08      2749103.28     10198703.64
      2749005.69     10198153.13
#Sta/Elev= 30
  4681.8 1256.69  4703.4 1256.56  4781.9 1251.25  4852.4 1243.17  4866.9 1245.28
  4881.3 1244.87  4902.1 1241.50  4945.4 1239.83  4966.2 1235.87  4977.6 1235.29
  4978.1 1234.79  4983.6 1235.29  5020.9 1236.54  5112.3 1235.96  5128.5 1237.78
  5133.6 1236.04  5163.0 1237.81  5173.2 1240.01  5213.8 1239.82  5241.6 1242.44
  5246.7 1241.26  5274.8 1245.54  5295.1 1244.97  5354.8 1252.00  5366.2 1250.75
  5406.8 1253.21  5437.2 1252.23  5473.0 1254.89  5538.8 1255.61  5559.1 1257.87
#Mann=3,-1,0
  4681.8    0.05       0  4977.6    0.03       0  4983.6    0.05       0
Bank Sta=4977.6,4983.6
Exp/Cntr=0.3,0.1

Type RM Length L Ch R = 1,1000,0,0,0
BEGIN DESCRIPTION:
HICKORY15 2.0
END DESCRIPTION:
XS GIS Cut Line= 3
      2749046.09     10199445.13      2749345.51     10199131.65
      2749490.72     10198850.65
#Sta/Elev= 30
  4566.5 1260.69  4610.2 1261.31  4617.1 1262.69  4631.3 1261.11  4687.9 1261.08
  4702.1 1259.41  4744.5 1257.35  4758.7 1255.27  4779.7 1255.44  4787.0 1253.75
  4836.4 1248.55  4907.1 1243.64  4921.3 1243.59  4928.5 1239.97  4935.4 1240.97
  4942.7 1236.02  4953.5 1233.53  4954.0 1233.03  4959.5 1233.53  4970.6 1234.50
  5029.8 1234.49  5101.8 1237.95  5140.5 1244.44  5146.1 1243.51  5201.0 1246.10
  5234.7 1244.71  5245.6 1245.62  5251.2 1247.34  5267.8 1248.41  5316.3 1248.84
#Mann=3,-1,0
  4566.5    0.05       0  4953.5    0.03       0  4959.5    0.05       0
Bank Sta=4953.5,4959.5
Exp/Cntr=0.3,0.1

Chan Stop Cuts=-1