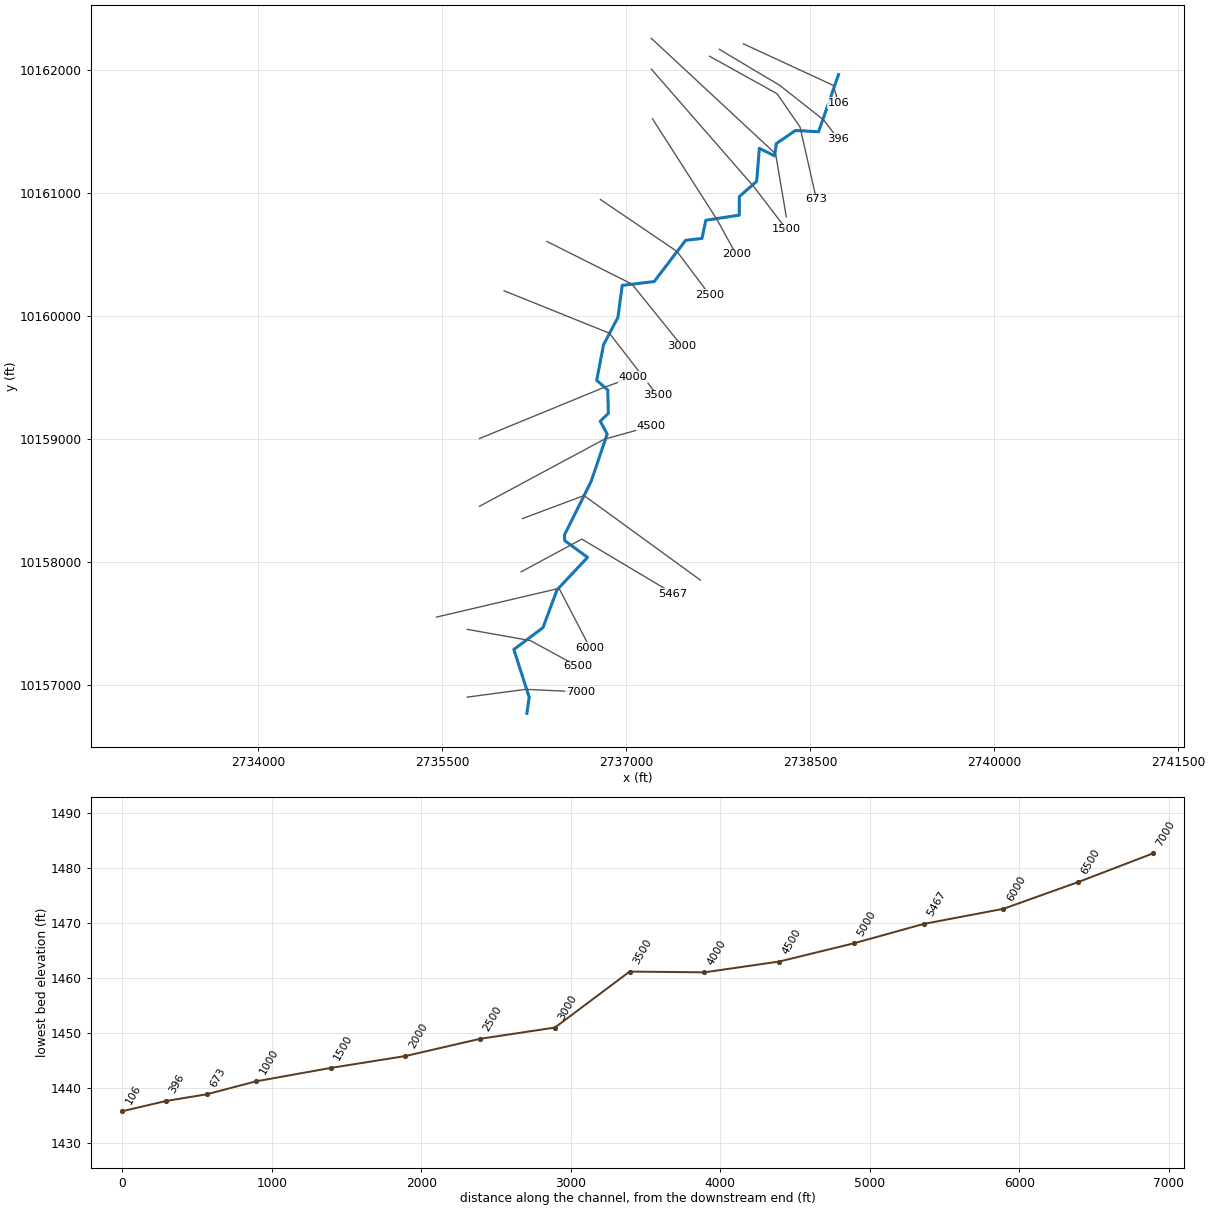
--- HICKORY23.prj (project) ---

Proj Title=HICKORY23 Base Level Engineering
Current Plan=p01
Default Exp/Contr=0.3,0.1
English Units
Geom File=g01
Flow File=f01
Plan File=p01
BEGIN DESCRIPTION:
HICKORY23
END DESCRIPTION:

--- HICKORY23.p01 (plan) ---

Plan Title=Multiple Run
Short Identifier=Multiple
Geom File=g01
Flow File=f01
Subcritical Flow
K Sum by GR= 0
Std Step Tol= 0.01
Critical Tol= 0.01
Num of Std Step Trials= 20
Max Error Tol= 0.3
Flow Tol Ratio= 0.001
Split Flow NTrial= 30
Split Flow Tol= 0.02
Split Flow Ratio= 0.02
Log Output Level= 0
Friction Slope Method= 1
Unsteady Friction Slope Method= 2
Unsteady Bridges Friction Slope Method= 1
Parabolic Critical Depth
Global Vel Dist=  1 , 1 , 1
Global Log Level= 0
CheckData=True
Encroach Param= -1, 0, 0, 0
BEGIN DESCRIPTION:
Multiple Run
END DESCRIPTION:

--- HICKORY23.f01 (steady flow) ---

Flow Title=Multiple
Number of Profiles=7
Profile Names=10-year,25-year,50-year,1pct_min,100-year,1pct_plu,500-year
River Rch & RM= HICKORY23,Reach-1,7000
     469     765    1089     807    1467    2667    2036
River Rch & RM= HICKORY23,Reach-1,4000
     604    1006    1354     949    1832    3536    2535
Boundary for River Rch & Prof#=HICKORY23,Reach-1,1
Up Type=0
Dn Type=3
Dn Slope=0.005
Boundary for River Rch & Prof#=HICKORY23,Reach-1,2
Up Type=0
Dn Type=3
Dn Slope=0.005
Boundary for River Rch & Prof#=HICKORY23,Reach-1,3
Up Type=0
Dn Type=3
Dn Slope=0.005
Boundary for River Rch & Prof#=HICKORY23,Reach-1,4
Up Type=0
Dn Type=3
Dn Slope=0.005
Boundary for River Rch & Prof#=HICKORY23,Reach-1,5
Up Type=0
Dn Type=3
Dn Slope=0.005
Boundary for River Rch & Prof#=HICKORY23,Reach-1,6
Up Type=0
Dn Type=3
Dn Slope=0.005
Boundary for River Rch & Prof#=HICKORY23,Reach-1,7
Up Type=0
Dn Type=3
Dn Slope=0.005

--- HICKORY23.g01 (geometry) ---

Geom Title=Existing Conditions

River Reach=HICKORY23,Reach-1
Reach XY= 30
      2736191.50     10156771.00      2736210.00     10156903.00
      2736085.00     10157290.00      2736322.50     10157467.00
      2736437.25     10157774.00      2736685.75     10158038.00
      2736499.75     10158174.00      2736497.50     10158219.00
      2736716.00     10158657.00      2736845.75     10159039.00
      2736789.25     10159144.00      2736855.25     10159207.00
      2736850.75     10159397.00      2736760.50     10159476.00
      2736816.25     10159765.00      2736933.00     10159986.00
      2736968.50     10160247.00      2737228.75     10160278.00
      2737486.00     10160613.00      2737618.50     10160628.00
      2737649.75     10160776.00      2737922.50     10160817.00
      2737922.50     10160967.00      2738064.25     10161092.00
      2738086.00     10161360.00      2738210.00     10161299.00
      2738224.75     10161399.00      2738381.00     10161505.00
      2738568.50     10161494.00      2738731.50     10161959.00

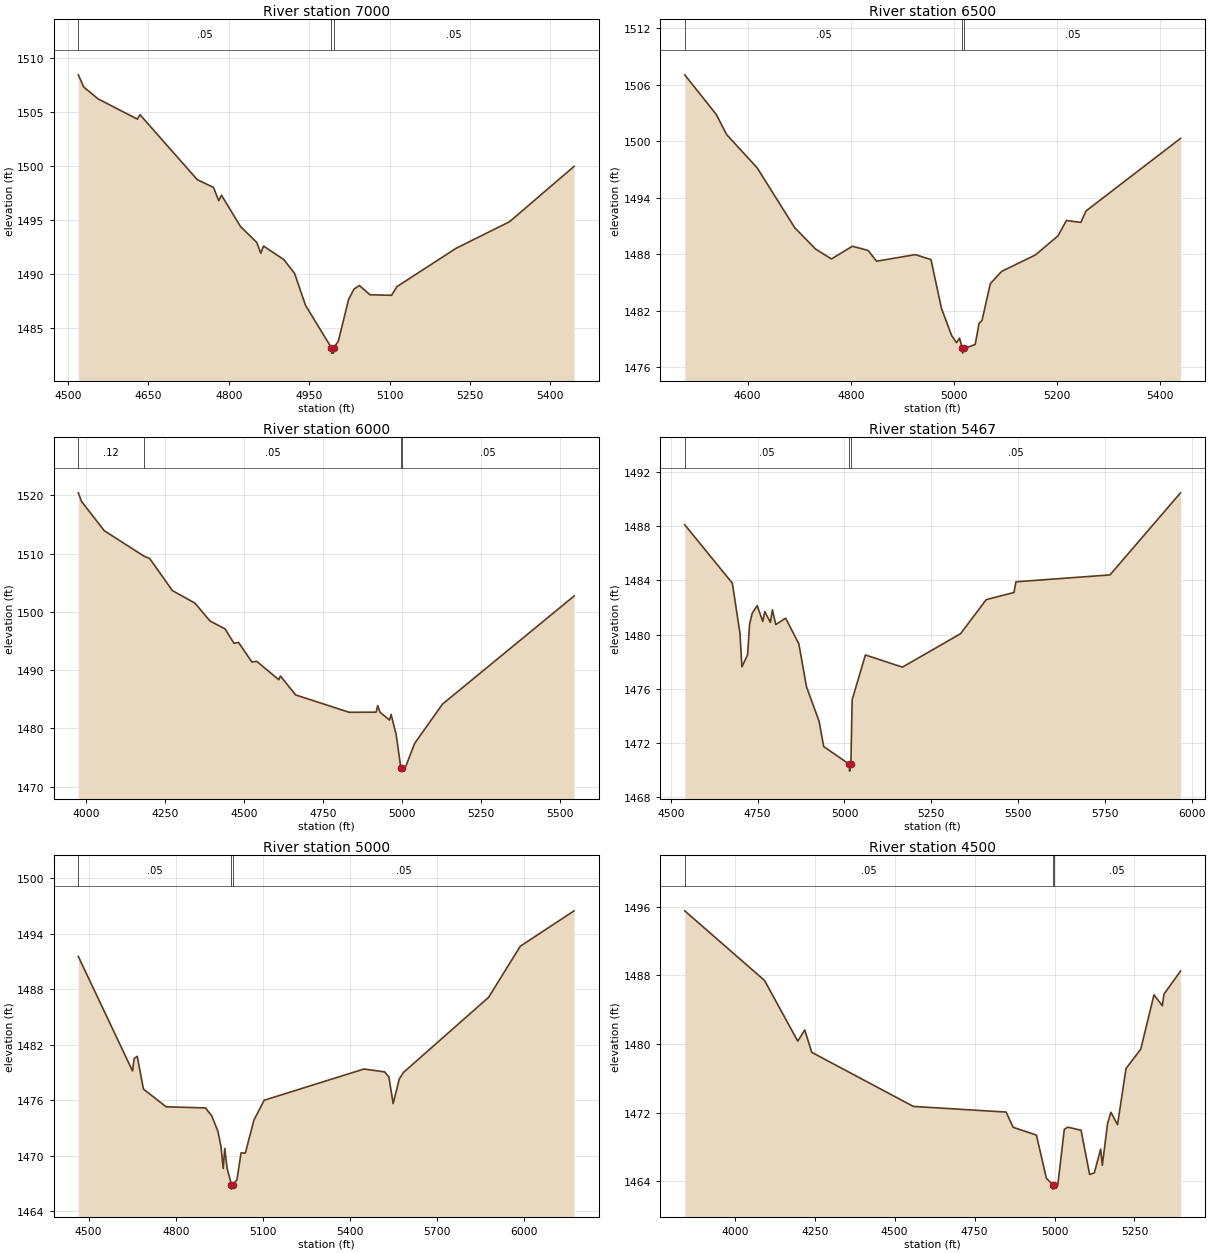
Type RM Length L Ch R = 1,7000,500,500,500
BEGIN DESCRIPTION:
HICKORY23 14.0
END DESCRIPTION:
XS GIS Cut Line= 3
      2735705.68     10156903.11      2736182.22     10156966.21
      2736625.94     10156945.57
#Sta/Elev= 30
  4519.3 1508.47  4529.4 1507.34  4556.0 1506.25  4629.4 1504.37  4634.4 1504.78
  4741.2 1498.77  4771.5 1498.05  4781.2 1496.83  4786.3 1497.33  4821.9 1494.43
  4852.2 1492.96  4859.7 1491.96  4864.7 1492.63  4902.6 1491.38  4922.8 1490.09
  4943.2 1487.14  4991.4 1483.22  4991.7 1482.72  4995.2 1482.72  4995.4 1483.22
  5004.2 1483.80  5023.5 1487.69  5033.5 1488.64  5043.5 1488.98  5063.5 1488.12
  5103.6 1488.07  5113.6 1488.87  5223.7 1492.41  5323.8 1494.88  5444.2 1500.00
#Mann=3,-1,0
  4519.3    0.05       0  4991.4    0.05       0  4995.4    0.05       0
Bank Sta=4991.4,4995.4
Exp/Cntr=0.3,0.1

Type RM Length L Ch R = 1,6500,500,500,500
BEGIN DESCRIPTION:
HICKORY23 13.0
END DESCRIPTION:
XS GIS Cut Line= 3
      2735705.65     10157453.12      2736219.46     10157362.19
      2736605.70     10157153.10
#Sta/Elev= 30
  4478.2 1507.06  4539.2 1502.86  4559.4 1500.72  4618.5 1497.19  4691.5 1490.82
  4731.8 1488.56  4762.6 1487.51  4803.2 1488.86  4833.7 1488.41  4850.1 1487.27
  4925.1 1487.97  4955.5 1487.44  4975.9 1482.25  4995.5 1479.38  5005.0 1478.62
  5010.7 1479.10  5016.4 1478.01  5016.7 1477.51  5020.4 1478.01  5041.2 1478.43
  5048.7 1480.67  5054.4 1480.98  5070.6 1484.89  5092.5 1486.19  5158.1 1487.94
  5201.8 1489.97  5218.0 1491.59  5245.9 1491.39  5256.1 1492.61  5439.2 1500.31
#Mann=3,-1,0
  4478.2    0.05       0  5016.4    0.05       0  5020.4    0.05       0
Bank Sta=5016.4,5020.4
Exp/Cntr=0.3,0.1

Type RM Length L Ch R = 1,6000,533,533,533
BEGIN DESCRIPTION:
HICKORY23 12.0
END DESCRIPTION:
XS GIS Cut Line= 3
      2735455.70     10157553.12      2736453.67     10157786.09
      2736705.70     10157303.09
#Sta/Elev= 30
  3975.2 1520.42  3985.4 1518.94  4057.3 1513.92  4184.0 1509.52  4201.1 1509.15
  4273.0 1503.64  4344.4 1501.49  4392.1 1498.42  4439.7 1497.07  4468.1 1494.59
  4482.3 1494.75  4524.8 1491.38  4540.0 1491.50  4609.9 1488.34  4615.0 1488.98
  4663.2 1485.73  4832.8 1482.75  4917.9 1482.77  4923.0 1483.90  4930.2 1482.77
  4960.4 1481.42  4965.5 1482.39  4981.5 1478.90  4996.5 1473.15  4996.7 1472.65
  5000.5 1473.15  5012.1 1473.50  5039.8 1477.40  5128.2 1484.16  5544.8 1502.71
#Mann=4,-1,0
  3975.2    0.12       0  4184.0    0.05       0  4996.5    0.05       0
  5000.5    0.05       0
Bank Sta=4996.5,5000.5
Exp/Cntr=0.3,0.1

Type RM Length L Ch R = 1,5467,467,467,467
BEGIN DESCRIPTION:
Mapping XS 022d9bd0
END DESCRIPTION:
XS GIS Cut Line= 3
      2736144.64     10157920.68      2736639.42     10158186.30
      2737384.21     10157743.60
#Sta/Elev= 30
  4540.0 1488.12  4677.1 1483.80  4699.1 1480.09  4704.7 1477.61  4721.0 1478.50
  4726.7 1480.75  4734.1 1481.56  4748.6 1482.14  4764.8 1480.97  4770.5 1481.70
  4786.7 1480.90  4792.4 1481.83  4802.2 1480.74  4830.6 1481.21  4868.7 1479.31
  4890.7 1476.14  4927.1 1473.58  4940.2 1471.72  5014.5 1470.40  5014.8 1469.90
  5018.5 1470.40  5022.2 1475.18  5060.4 1478.49  5167.0 1477.59  5334.3 1480.06
  5408.3 1482.58  5488.2 1483.11  5494.0 1483.90  5764.8 1484.41  5968.0 1490.48
#Mann=3,-1,0
  4540.0    0.05       0  5014.5    0.05       0  5018.5    0.05       0
Bank Sta=5014.5,5018.5
Exp/Cntr=0.3,0.1

Type RM Length L Ch R = 1,5000,500,500,500
BEGIN DESCRIPTION:
HICKORY23 10.0
END DESCRIPTION:
XS GIS Cut Line= 3
      2736155.66     10158353.10      2736657.45     10158540.11
      2737605.65     10157853.14
#Sta/Elev= 30
  4464.5 1491.56  4651.0 1479.17  4656.6 1480.52  4667.3 1480.76  4688.6 1477.21
  4766.9 1475.29  4902.1 1475.17  4923.4 1474.32  4944.8 1472.66  4955.4 1471.03
  4963.2 1468.61  4968.5 1470.79  4976.8 1468.60  4991.5 1466.88  4991.8 1466.38
  4995.5 1466.88  5010.2 1467.35  5024.6 1470.30  5039.3 1470.28  5068.7 1473.84
  5104.2 1476.00  5447.6 1479.38  5518.7 1479.07  5533.4 1478.52  5548.1 1475.64
  5569.0 1478.29  5583.6 1479.01  5876.7 1487.14  5985.7 1492.67  6170.9 1496.50
#Mann=3,-1,0
  4464.5    0.05       0  4991.5    0.05       0  4995.5    0.05       0
Bank Sta=4991.5,4995.5
Exp/Cntr=0.3,0.1

Type RM Length L Ch R = 1,4500,500,500,500
BEGIN DESCRIPTION:
HICKORY23 9.0
END DESCRIPTION:
XS GIS Cut Line= 3
      2735805.73     10158453.13      2736825.64     10158998.78
      2737205.68     10159103.11
#Sta/Elev= 30
  3843.3 1495.53  4092.8 1487.41  4196.8 1480.33  4218.7 1481.63  4240.6 1479.02
  4558.4 1472.71  4848.6 1472.05  4870.5 1470.27  4943.3 1469.37  4974.5 1464.34
  4994.5 1463.56  4994.7 1463.06  4998.5 1463.56  5010.4 1463.59  5030.6 1470.04
  5041.5 1470.29  5083.0 1469.93  5109.9 1464.77  5124.5 1464.96  5144.3 1467.73
  5149.5 1465.85  5166.0 1470.74  5176.3 1472.03  5197.1 1470.58  5223.6 1477.13
  5269.7 1479.39  5311.1 1485.73  5337.3 1484.46  5342.4 1485.81  5394.1 1488.50
#Mann=3,-1,0
  3843.3    0.05       0  4994.5    0.05       0  4998.5    0.05       0
Bank Sta=4994.5,4998.5
Exp/Cntr=0.3,0.1

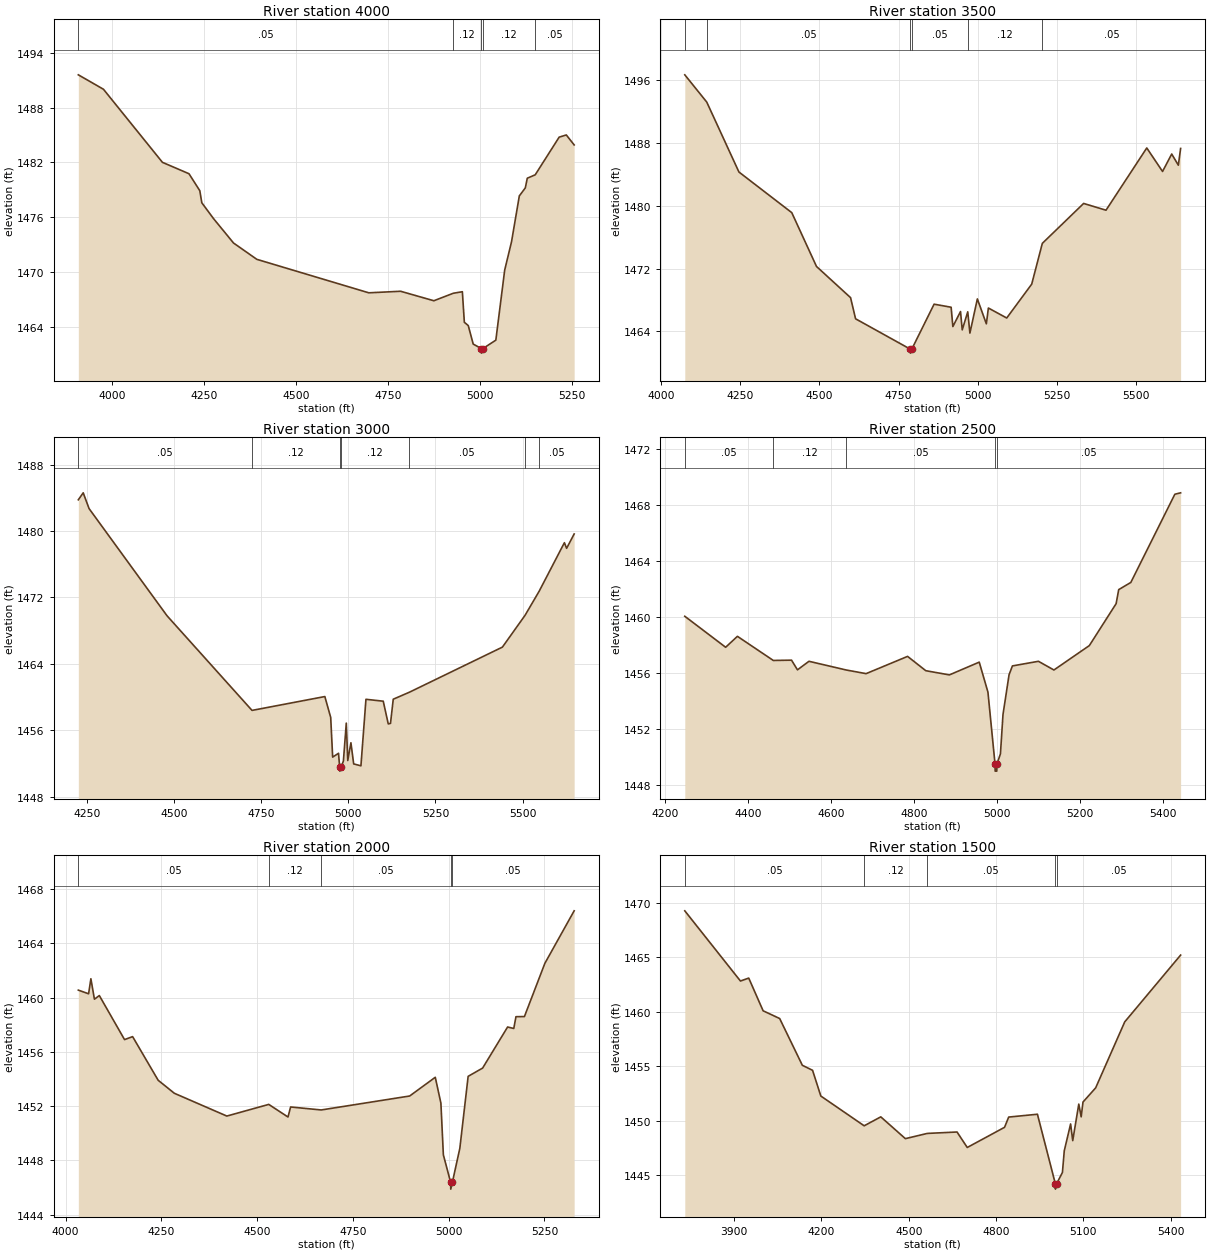
Type RM Length L Ch R = 1,4000,500,500,500
BEGIN DESCRIPTION:
HICKORY23 8.0
END DESCRIPTION:
XS GIS Cut Line= 3
      2735805.65     10159003.10      2736815.87     10159416.40
      2737055.68     10159503.11
#Sta/Elev= 30
  3908.5 1491.60  3976.7 1490.02  4136.9 1482.01  4209.0 1480.76  4238.4 1478.90
  4243.8 1477.58  4275.9 1475.83  4329.9 1473.17  4393.2 1471.38  4697.3 1467.71
  4783.7 1467.88  4874.0 1466.84  4926.7 1467.66  4951.4 1467.83  4956.8 1464.48
  4967.4 1464.12  4980.9 1462.09  5003.0 1461.60  5003.3 1461.10  5007.2 1461.60
  5042.3 1462.52  5066.4 1470.21  5084.9 1473.30  5106.1 1478.33  5122.4 1479.21
  5127.7 1480.27  5149.2 1480.64  5214.3 1484.77  5233.7 1485.01  5255.0 1483.92
#Mann=5,-1,0
  3908.5    0.05       0  4926.7    0.12       0  5003.0    0.07       0
  5007.2    0.12       0  5149.2    0.05       0
Bank Sta=5003,5007.2
Exp/Cntr=0.3,0.1

Type RM Length L Ch R = 1,3500,500,500,500
BEGIN DESCRIPTION:
HICKORY23 7.0
END DESCRIPTION:
XS GIS Cut Line= 3
      2736005.66     10160203.12      2736863.69     10159858.63
      2737255.69     10159353.11
#Sta/Elev= 30
  4075.4 1496.66  4144.7 1493.19  4246.2 1484.29  4412.9 1479.12  4490.9 1472.27
  4598.4 1468.30  4614.2 1465.61  4787.1 1461.74  4787.4 1461.24  4791.5 1461.74
  4861.9 1467.47  4915.7 1467.08  4921.1 1464.62  4945.3 1466.53  4950.7 1464.20
  4968.1 1466.50  4974.9 1463.79  4998.4 1468.14  5026.8 1464.97  5033.2 1466.98
  5091.1 1465.71  5169.9 1470.02  5203.4 1475.21  5333.7 1480.29  5404.3 1479.43
  5532.9 1487.35  5582.7 1484.36  5611.6 1486.58  5632.5 1485.16  5639.7 1487.29
#Mann=6,-1,0
  4075.4    0.12       0  4144.7    0.05       0  4787.1    0.07       0
  4791.5    0.05       0  4968.1    0.12       0  5203.4    0.05       0
Bank Sta=4787.1,4791.5
Exp/Cntr=0.3,0.1

Type RM Length L Ch R = 1,3000,500,500,500
BEGIN DESCRIPTION:
HICKORY23 6.0
END DESCRIPTION:
XS GIS Cut Line= 3
      2736355.66     10160603.13      2737048.26     10160256.72
      2737455.70     10159753.10
#Sta/Elev= 30
  4225.6 1483.77  4239.6 1484.61  4256.4 1482.71  4480.0 1469.79  4723.8 1458.38
  4932.7 1460.05  4949.5 1457.53  4955.1 1452.75  4971.9 1453.21  4975.2 1451.56
  4975.5 1451.06  4979.6 1451.56  4985.9 1452.28  4994.2 1456.85  4998.4 1452.34
  5007.5 1454.48  5015.4 1451.93  5036.2 1451.70  5050.6 1459.72  5100.2 1459.49
  5114.6 1456.75  5121.0 1456.82  5128.9 1459.73  5175.1 1460.57  5442.0 1466.01
  5506.9 1469.84  5547.6 1472.76  5619.8 1478.60  5626.2 1477.92  5647.8 1479.65
#Mann=7,-1,0
  4225.6    0.05       0  4723.8    0.12       0  4975.2    0.07       0
  4979.6    0.12       0  5175.1    0.05       0  5506.9    0.12       0
  5547.6    0.05       0
Bank Sta=4975.2,4979.6
Exp/Cntr=0.3,0.1

Type RM Length L Ch R = 1,2500,500,500,500
BEGIN DESCRIPTION:
HICKORY23 5.0
END DESCRIPTION:
XS GIS Cut Line= 3
      2736790.57     10160944.30      2737414.04     10160523.12
      2737680.67     10160169.10
#Sta/Elev= 30
  4247.6 1460.06  4346.1 1457.85  4374.5 1458.63  4461.0 1456.91  4505.0 1456.93
  4519.3 1456.24  4547.0 1456.85  4636.8 1456.23  4684.8 1455.97  4784.8 1457.20
  4828.7 1456.18  4885.6 1455.88  4957.6 1456.79  4978.6 1454.65  4995.7 1449.52
  4996.0 1449.02  4999.9 1449.02  5000.2 1449.52  5008.7 1450.25  5014.9 1453.06
  5029.5 1455.89  5037.6 1456.52  5100.3 1456.85  5137.7 1456.23  5223.1 1457.97
  5287.7 1460.96  5293.9 1461.96  5323.1 1462.47  5429.3 1468.76  5443.2 1468.86
#Mann=5,-1,0
  4247.6    0.05       0  4461.0    0.12       0  4636.8    0.05       0
  4995.7    0.05       0  5000.2    0.05       0
Bank Sta=4995.7,5000.2
Exp/Cntr=0.3,0.1

Type RM Length L Ch R = 1,2000,500,500,500
BEGIN DESCRIPTION:
HICKORY23 4.0
END DESCRIPTION:
XS GIS Cut Line= 3
      2737215.24     10161599.20      2737737.94     10160786.00
      2737896.75     10160499.58
#Sta/Elev= 30
  4033.3 1460.56  4060.1 1460.29  4066.1 1461.40  4075.3 1459.89  4088.1 1460.16
  4153.9 1456.91  4175.0 1457.13  4241.7 1453.91  4284.0 1452.95  4420.9 1451.27
  4530.3 1452.13  4580.6 1451.20  4587.4 1451.94  4667.3 1451.72  4898.2 1452.75
  4965.0 1454.13  4979.7 1452.22  4986.1 1448.41  5005.1 1446.38  5005.4 1445.88
  5009.6 1446.38  5029.1 1448.89  5050.8 1454.20  5088.6 1454.81  5153.8 1457.84
  5169.9 1457.73  5175.6 1458.60  5197.7 1458.61  5251.1 1462.54  5327.5 1466.41
#Mann=5,-1,0
  4033.3    0.05       0  4530.3    0.12       0  4667.3    0.05       0
  5005.1    0.05       0  5009.6    0.05       0
Bank Sta=5005.1,5009.6
Exp/Cntr=0.3,0.1

Type RM Length L Ch R = 1,1500,500,500,500
BEGIN DESCRIPTION:
HICKORY23 3.0
END DESCRIPTION:
XS GIS Cut Line= 3
      2737205.69     10162003.11      2738041.41     10161047.76
      2738305.68     10160703.12
#Sta/Elev= 30
  3730.7 1469.25  3921.9 1462.81  3950.4 1463.08  3999.8 1460.08  4056.7 1459.37
  4134.6 1455.08  4169.7 1454.62  4198.1 1452.26  4347.0 1449.53  4404.1 1450.35
  4488.6 1448.35  4563.8 1448.83  4666.1 1448.96  4701.2 1447.54  4829.3 1449.39
  4843.6 1450.33  4942.3 1450.59  5003.8 1444.22  5004.1 1443.72  5008.3 1444.22
  5028.2 1445.25  5034.5 1447.23  5056.3 1449.70  5063.6 1448.17  5084.4 1451.52
  5092.6 1450.35  5098.9 1451.71  5142.4 1453.01  5242.2 1459.06  5434.3 1465.19
#Mann=5,-1,0
  3730.7    0.05       0  4347.0    0.12       0  4563.8    0.05       0
  5003.8    0.05       0  5008.3    0.05       0
Bank Sta=5003.8,5008.3
Exp/Cntr=0.3,0.1

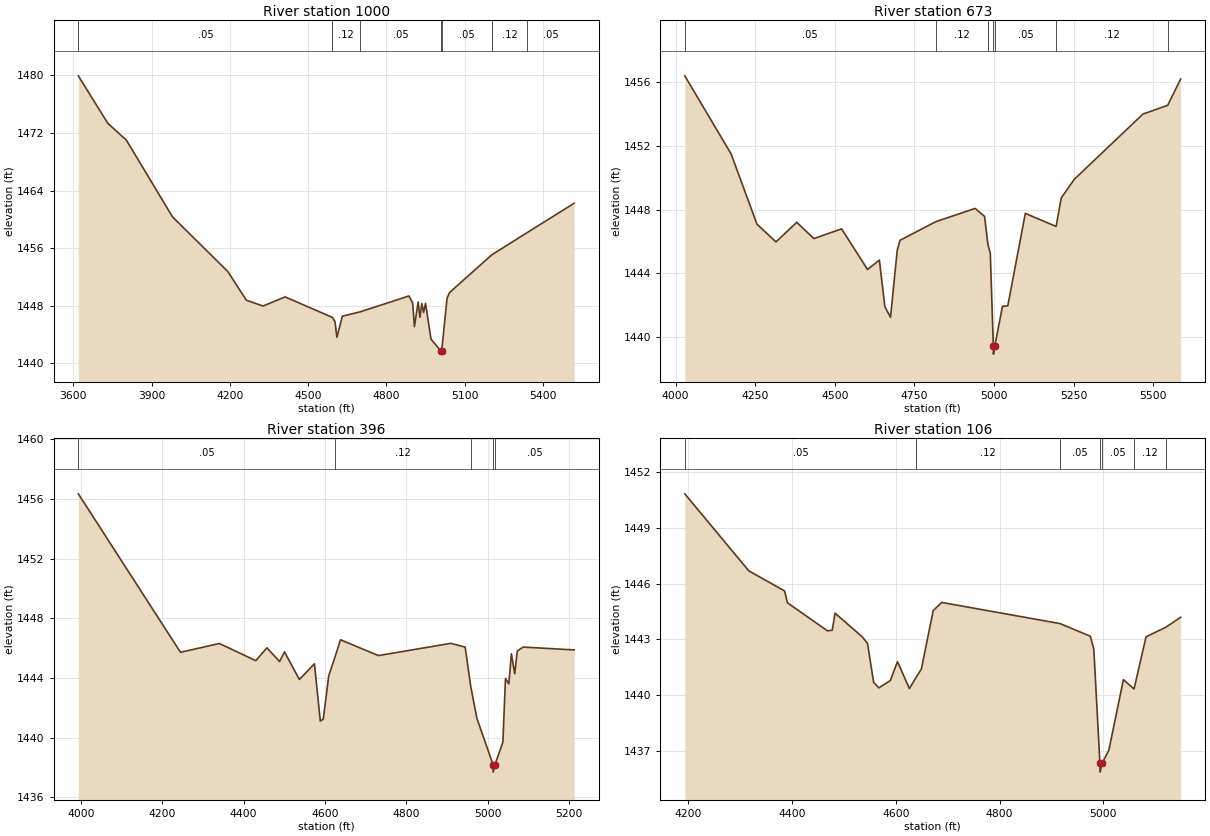
Type RM Length L Ch R = 1,1000,327,327,327
BEGIN DESCRIPTION:
HICKORY23 2.0
END DESCRIPTION:
XS GIS Cut Line= 3
      2737205.71     10162253.09      2738218.66     10161314.86
      2738305.68     10160803.11
#Sta/Elev= 30
  3619.3 1479.94  3732.4 1473.34  3803.3 1471.01  3980.1 1460.35  4192.2 1452.75
  4263.1 1448.77  4327.1 1447.96  4411.6 1449.23  4592.9 1446.38  4602.7 1445.80
  4610.0 1443.62  4631.0 1446.55  4698.8 1447.15  4886.1 1449.36  4900.3 1448.38
  4907.1 1445.10  4921.3 1448.53  4928.1 1446.39  4935.5 1448.32  4942.3 1447.07
  4949.7 1448.34  4970.6 1443.36  5007.2 1441.78  5007.5 1441.28  5011.7 1441.78
  5032.2 1449.08  5042.4 1449.86  5203.4 1455.07  5339.5 1458.17  5519.1 1462.24
#Mann=7,-1,0
  3619.3    0.05       0  4592.9    0.12       0  4698.8    0.05       0
  5007.2    0.05       0  5011.7    0.05       0  5203.4    0.12       0
  5339.5    0.05       0
Bank Sta=5007.2,5011.7
Exp/Cntr=0.3,0.1

Type RM Length L Ch R = 1,673,277,277,277
BEGIN DESCRIPTION:
Mapping XS 3e5eef4c
END DESCRIPTION:
XS GIS Cut Line= 4
      2737681.07     10162107.18      2738230.76     10161803.04
      2738417.74     10161532.72      2738550.52     10160947.60
#Sta/Elev= 30
  4029.0 1456.40  4174.4 1451.50  4255.7 1447.09  4315.3 1445.98  4380.5 1447.21
  4434.3 1446.19  4521.4 1446.80  4602.7 1444.25  4640.0 1444.84  4657.2 1441.92
  4675.0 1441.25  4696.0 1445.45  4704.8 1446.08  4817.2 1447.25  4940.6 1448.08
  4970.3 1447.58  4980.7 1445.83  4988.3 1445.27  4997.8 1439.44  4998.1 1438.94
  5002.4 1439.44  5026.5 1441.94  5043.2 1441.97  5098.3 1447.77  5194.9 1446.95
  5211.1 1448.74  5252.1 1449.91  5467.5 1454.00  5545.4 1454.55  5585.9 1456.20
#Mann=7,-1,0
  4029.0    0.05       0  4817.2    0.12       0  4980.7    0.05       0
  4997.8    0.05       0  5002.4    0.05       0  5194.9    0.12       0
  5545.4    0.05       0
Bank Sta=4997.8,5002.4
Exp/Cntr=0.3,0.1

Type RM Length L Ch R = 1,396,290,290,290
BEGIN DESCRIPTION:
Mapping XS da8975d8
END DESCRIPTION:
XS GIS Cut Line= 4
      2737759.92     10162163.49      2738253.29     10161870.63
      2738611.47     10161589.03      2738726.33     10161438.14
#Sta/Elev= 30
  3993.5 1456.35  4244.7 1445.73  4340.2 1446.32  4429.8 1445.17  4457.1 1446.03
  4488.3 1445.11  4500.3 1445.76  4537.0 1443.91  4574.0 1444.96  4588.4 1441.12
  4595.7 1441.25  4609.2 1444.17  4623.6 1445.34  4638.1 1446.57  4731.2 1445.51
  4909.2 1446.33  4944.5 1446.08  4958.4 1443.42  4973.4 1441.30  5013.2 1438.20
  5013.5 1437.70  5017.8 1438.20  5037.3 1439.71  5043.6 1443.97  5051.9 1443.62
  5058.2 1445.63  5066.4 1444.29  5072.7 1445.82  5087.2 1446.08  5212.5 1445.89
#Mann=5,-1,0
  3993.5    0.05       0  4623.6    0.12       0  4958.4    0.05       0
  5013.2    0.05       0  5017.8    0.05       0
Bank Sta=5013.2,5017.8
Exp/Cntr=0.3,0.1

Type RM Length L Ch R = 1,106,0,0,0
BEGIN DESCRIPTION:
HICKORY23 1.0
END DESCRIPTION:
XS GIS Cut Line= 3
      2737955.92     10162208.54      2738688.50     10161871.00
      2738730.69     10161728.10
#Sta/Elev= 30
  4193.4 1450.84  4316.8 1446.69  4385.7 1445.61  4391.3 1444.97  4468.4 1443.46
  4477.5 1443.49  4483.0 1444.41  4534.5 1443.16  4545.5 1442.79  4557.4 1440.68
  4567.5 1440.39  4589.5 1440.78  4603.3 1441.80  4626.3 1440.35  4639.1 1440.95
  4649.3 1441.40  4672.2 1444.55  4688.6 1444.99  4916.8 1443.85  4974.9 1443.17
  4981.7 1442.48  4993.4 1436.35  4993.7 1435.85  4998.0 1436.35  5010.6 1437.02
  5038.7 1440.83  5059.2 1440.33  5082.4 1443.14  5120.3 1443.65  5149.0 1444.19
#Mann=7,-1,0
  4193.4    0.05       0  4639.1    0.12       0  4916.8    0.05       0
  4993.4    0.05       0  4998.0    0.05       0  5059.2    0.12       0
  5120.3    0.05       0
Bank Sta=4993.4,4998
Exp/Cntr=0.3,0.1

Chan Stop Cuts=-1