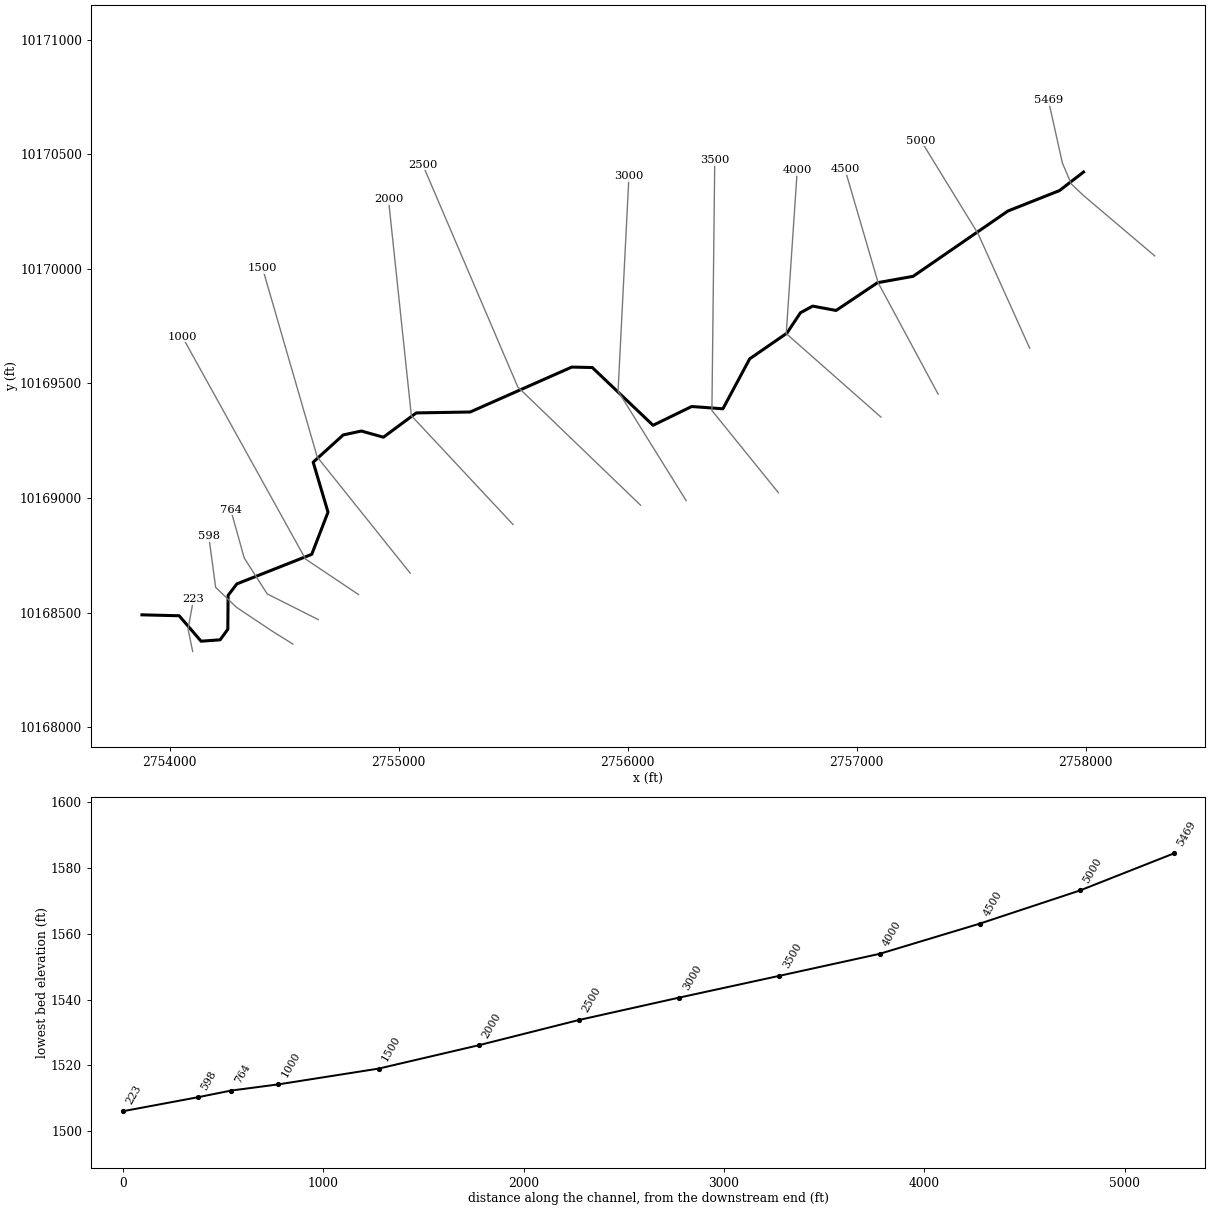
--- HICKORY25.prj (project) ---

Proj Title=HICKORY25 Base Level Engineering
Current Plan=p01
Default Exp/Contr=0.3,0.1
English Units
Geom File=g01
Flow File=f01
Plan File=p01
BEGIN DESCRIPTION:
HICKORY25
END DESCRIPTION:

--- HICKORY25.p01 (plan) ---

Plan Title=Multiple Run
Short Identifier=Multiple
Geom File=g01
Flow File=f01
Subcritical Flow
K Sum by GR= 0
Std Step Tol= 0.01
Critical Tol= 0.01
Num of Std Step Trials= 20
Max Error Tol= 0.3
Flow Tol Ratio= 0.001
Split Flow NTrial= 30
Split Flow Tol= 0.02
Split Flow Ratio= 0.02
Log Output Level= 0
Friction Slope Method= 1
Unsteady Friction Slope Method= 2
Unsteady Bridges Friction Slope Method= 1
Parabolic Critical Depth
Global Vel Dist=  1 , 1 , 1
Global Log Level= 0
CheckData=True
Encroach Param= -1, 0, 0, 0
BEGIN DESCRIPTION:
Multiple Run
END DESCRIPTION:

--- HICKORY25.f01 (steady flow) ---

Flow Title=Multiple
Number of Profiles=7
Profile Names=10-year,25-year,50-year,1pct_min,100-year,1pct_plu,500-year
River Rch & RM= HICKORY25,Reach-1,5469
     237     371     647     514     880    1507    1276
Boundary for River Rch & Prof#=HICKORY25,Reach-1,1
Up Type=0
Dn Type=3
Dn Slope=0.005
Boundary for River Rch & Prof#=HICKORY25,Reach-1,2
Up Type=0
Dn Type=3
Dn Slope=0.005
Boundary for River Rch & Prof#=HICKORY25,Reach-1,3
Up Type=0
Dn Type=3
Dn Slope=0.005
Boundary for River Rch & Prof#=HICKORY25,Reach-1,4
Up Type=0
Dn Type=3
Dn Slope=0.005
Boundary for River Rch & Prof#=HICKORY25,Reach-1,5
Up Type=0
Dn Type=3
Dn Slope=0.005
Boundary for River Rch & Prof#=HICKORY25,Reach-1,6
Up Type=0
Dn Type=3
Dn Slope=0.005
Boundary for River Rch & Prof#=HICKORY25,Reach-1,7
Up Type=0
Dn Type=3
Dn Slope=0.005

--- HICKORY25.g01 (geometry) ---

Geom Title=Existing Conditions

River Reach=HICKORY25,Reach-1
Reach XY= 30
      2757990.75     10170422.00      2757885.50     10170341.00
      2757660.75     10170252.00      2757246.50     10169967.00
      2757090.75     10169939.00      2756910.25     10169818.00
      2756808.00     10169837.00      2756754.50     10169808.00
      2756695.50     10169719.00      2756533.00     10169607.00
      2756416.00     10169389.00      2756279.75     10169399.00
      2756111.00     10169317.00      2755845.75     10169569.00
      2755756.25     10169571.00      2755312.50     10169375.00
      2755077.00     10169371.00      2754933.50     10169265.00
      2754837.50     10169292.00      2754758.25     10169275.00
      2754627.00     10169156.00      2754691.75     10168938.00
      2754620.75     10168754.00      2754293.75     10168625.00
      2754255.50     10168575.00      2754254.25     10168427.00
      2754220.75     10168381.00      2754137.50     10168375.00
      2754041.75     10168486.00      2753879.25     10168490.00

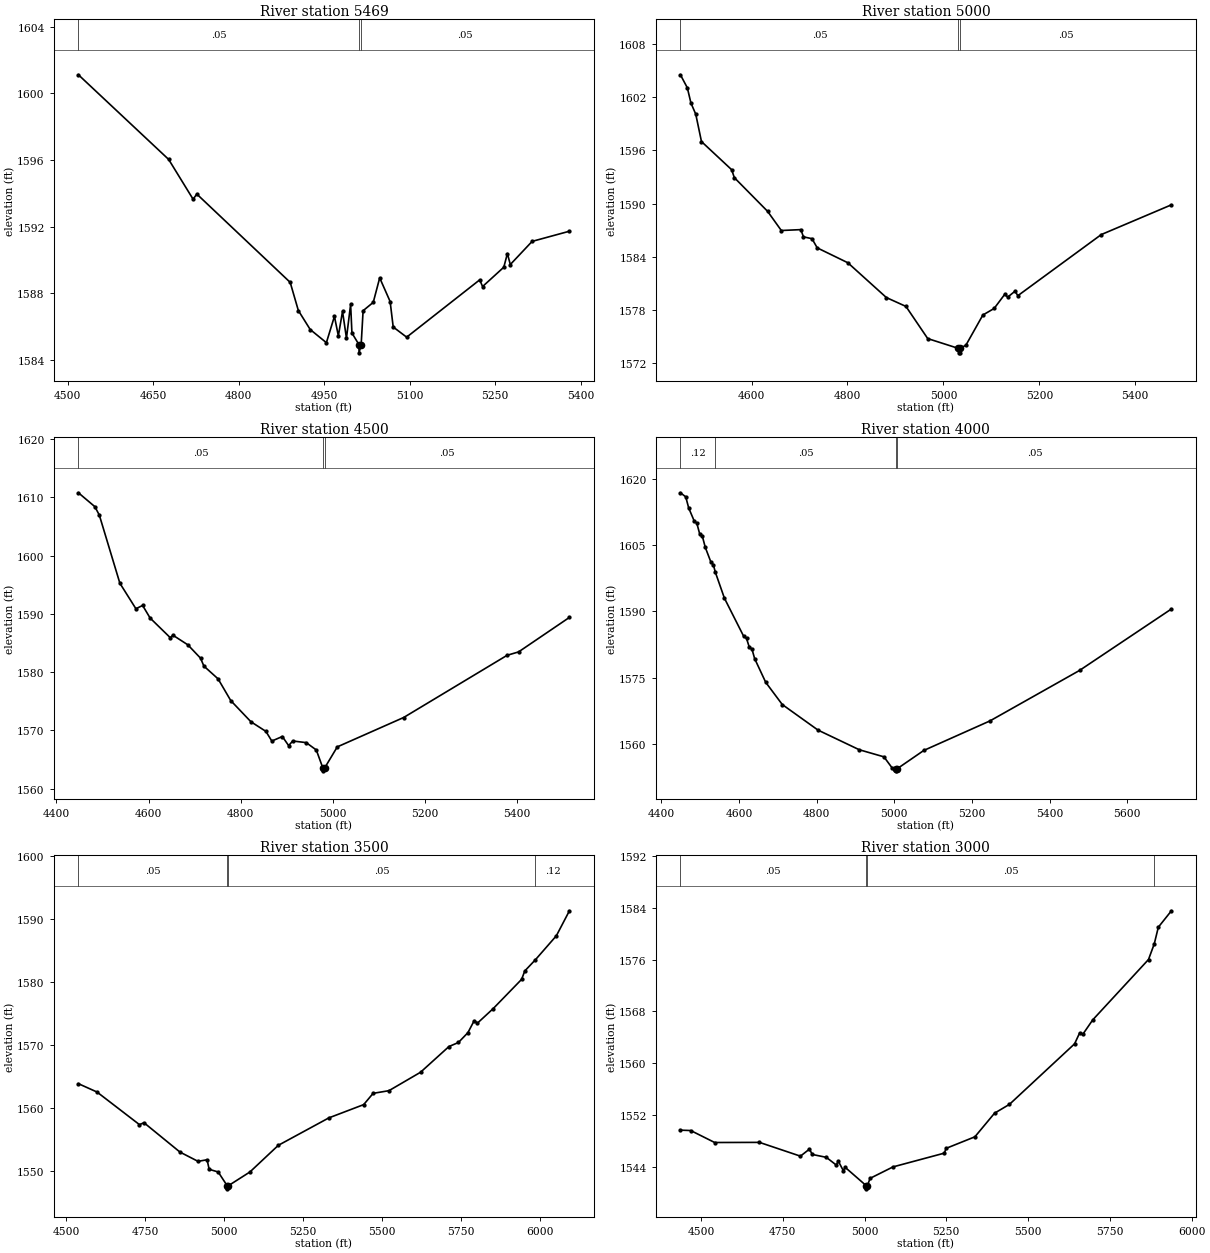
Type RM Length L Ch R = 1,5469,469,469,469
BEGIN DESCRIPTION:
HICKORY25 11.0
END DESCRIPTION:
XS GIS Cut Line= 5
      2758301.76     10170056.00      2757989.51     10170320.40
      2757937.25     10170370.00      2757898.24     10170461.86
      2757837.25     10170735.44
#Sta/Elev= 30
  4518.8 1601.11  4677.1 1596.03  4720.0 1593.64  4726.5 1593.95  4890.3 1588.65
  4904.6 1586.96  4925.4 1585.82  4953.8 1585.03  4967.9 1586.61  4974.8 1585.44
  4982.1 1586.91  4989.0 1585.30  4996.3 1587.33  4998.6 1585.61  5010.8 1584.92
  5011.1 1584.42  5014.8 1584.92  5018.2 1586.95  5036.0 1587.45  5047.3 1588.92
  5065.6 1587.50  5071.0 1585.97  5094.6 1585.36  5222.7 1588.80  5227.8 1588.40
  5265.0 1589.56  5271.3 1590.38  5276.4 1589.72  5314.7 1591.11  5380.1 1591.72
#Mann=3,-1,0
  4518.8    0.05       0  5010.8    0.05       0  5014.8    0.05       0
Bank Sta=5010.8,5014.8
Exp/Cntr=0.3,0.1

Type RM Length L Ch R = 1,5000,500,500,500
BEGIN DESCRIPTION:
HICKORY25 10.0
END DESCRIPTION:
XS GIS Cut Line= 3
      2757755.70     10169653.07      2757530.18     10170152.95
      2757281.23     10170558.08
#Sta/Elev= 30
  4451.6 1604.54  4466.0 1603.07  4473.6 1601.34  4483.6 1600.09  4495.5 1597.00
  4558.5 1593.82  4564.0 1592.93  4633.3 1589.13  4662.0 1586.96  4702.7 1587.06
  4708.2 1586.24  4725.9 1586.04  4736.9 1585.00  4800.7 1583.32  4881.1 1579.39
  4921.9 1578.39  4967.3 1574.76  5031.4 1573.65  5031.6 1573.15  5035.1 1573.15
  5035.4 1573.65  5047.1 1574.03  5082.3 1577.42  5105.8 1578.16  5128.1 1579.77
  5134.0 1579.44  5149.4 1580.11  5155.2 1579.60  5329.2 1586.50  5475.5 1589.86
#Mann=3,-1,0
  4451.6    0.05       0  5031.4    0.05       0  5035.4    0.05       0
Bank Sta=5031.4,5035.4
Exp/Cntr=0.3,0.1

Type RM Length L Ch R = 1,4500,500,500,500
BEGIN DESCRIPTION:
HICKORY25 9.0
END DESCRIPTION:
XS GIS Cut Line= 3
      2757355.69     10169453.10      2757093.78     10169939.46
      2756949.34     10170433.07
#Sta/Elev= 30
  4447.6 1610.77  4483.3 1608.39  4493.0 1606.95  4537.7 1595.25  4572.5 1590.88
  4587.1 1591.44  4603.4 1589.28  4647.2 1585.91  4652.9 1586.34  4685.3 1584.69
  4712.9 1582.40  4720.2 1581.04  4751.0 1578.85  4778.6 1575.12  4822.4 1571.49
  4854.9 1569.84  4867.8 1568.18  4890.6 1568.96  4904.3 1567.40  4913.3 1568.19
  4942.5 1567.91  4964.4 1566.65  4978.6 1563.57  4978.8 1563.07  4982.6 1563.57
  5010.0 1567.18  5154.2 1572.22  5378.9 1582.89  5403.8 1583.47  5514.3 1589.39
#Mann=3,-1,0
  4447.6    0.05       0  4978.6    0.05       0  4982.6    0.05       0
Bank Sta=4978.6,4982.6
Exp/Cntr=0.3,0.1

Type RM Length L Ch R = 1,4000,500,500,500
BEGIN DESCRIPTION:
HICKORY25 8.0
END DESCRIPTION:
XS GIS Cut Line= 3
      2757105.66     10169353.13      2756692.54     10169717.14
      2756740.59     10170429.32
#Sta/Elev= 30
  4449.4 1616.88  4463.1 1615.96  4470.7 1613.44  4484.9 1610.49  4491.6 1610.00
  4499.2 1607.50  4505.8 1607.06  4513.4 1604.52  4527.6 1601.25  4534.3 1600.54
  4539.3 1598.89  4562.7 1593.00  4612.1 1584.40  4619.6 1583.88  4626.3 1582.03
  4633.9 1581.39  4640.5 1579.32  4669.0 1573.95  4711.7 1568.91  4803.7 1563.12
  4909.9 1558.67  4973.5 1557.06  4994.6 1554.54  5004.0 1554.39  5004.2 1553.89
  5008.0 1554.39  5076.1 1558.51  5246.5 1565.20  5477.1 1576.63  5713.8 1590.56
#Mann=4,-1,0
  4449.4    0.12       0  4539.3    0.05       0  5004.0    0.05       0
  5008.0    0.05       0
Bank Sta=5004,5008
Exp/Cntr=0.3,0.1

Type RM Length L Ch R = 1,3500,500,500,500
BEGIN DESCRIPTION:
HICKORY25 7.0
END DESCRIPTION:
XS GIS Cut Line= 3
      2756658.25     10169023.05      2756368.00     10169381.59
      2756380.48     10170474.42
#Sta/Elev= 30
  4538.7 1563.88  4597.5 1562.56  4731.9 1557.39  4746.3 1557.69  4860.4 1553.03
  4917.3 1551.57  4946.1 1551.82  4952.5 1550.31  4981.2 1549.88  5009.5 1547.71
  5009.8 1547.21  5013.5 1547.71  5081.5 1549.88  5171.5 1554.11  5331.5 1558.46
  5441.6 1560.56  5471.6 1562.35  5521.6 1562.77  5621.6 1565.69  5711.6 1569.77
  5741.6 1570.41  5771.6 1571.97  5791.6 1573.88  5801.6 1573.47  5851.6 1575.78
  5941.6 1580.42  5951.6 1581.75  5985.5 1583.54  6051.6 1587.33  6092.9 1591.29
#Mann=4,-1,0
  4538.7    0.05       0  5009.5    0.05       0  5013.5    0.05       0
  5985.5    0.12       0
Bank Sta=5009.5,5013.5
Exp/Cntr=0.3,0.1

Type RM Length L Ch R = 1,3000,500,500,500
BEGIN DESCRIPTION:
HICKORY25 6.0
END DESCRIPTION:
XS GIS Cut Line= 3
      2756255.45     10168988.36      2755958.24     10169466.16
      2756005.69     10170403.16
#Sta/Elev= 30
  4437.3 1549.66  4468.8 1549.60  4542.0 1547.75  4678.9 1547.77  4804.1 1545.64
  4831.5 1546.72  4840.7 1545.90  4883.2 1545.46  4913.9 1544.26  4919.7 1544.90
  4935.1 1543.41  4941.0 1543.91  5005.0 1541.09  5005.2 1540.59  5009.0 1541.09
  5017.0 1542.21  5087.1 1543.98  5244.2 1546.11  5249.2 1546.84  5337.4 1548.63
  5397.5 1552.28  5443.2 1553.65  5642.2 1563.00  5657.8 1564.70  5667.8 1564.51
  5697.8 1566.71  5868.1 1576.03  5885.7 1578.44  5898.1 1581.02  5938.2 1583.56
#Mann=4,-1,0
  4437.3    0.05       0  5005.0    0.05       0  5009.0    0.05       0
  5885.7    0.12       0
Bank Sta=5005,5009
Exp/Cntr=0.3,0.1

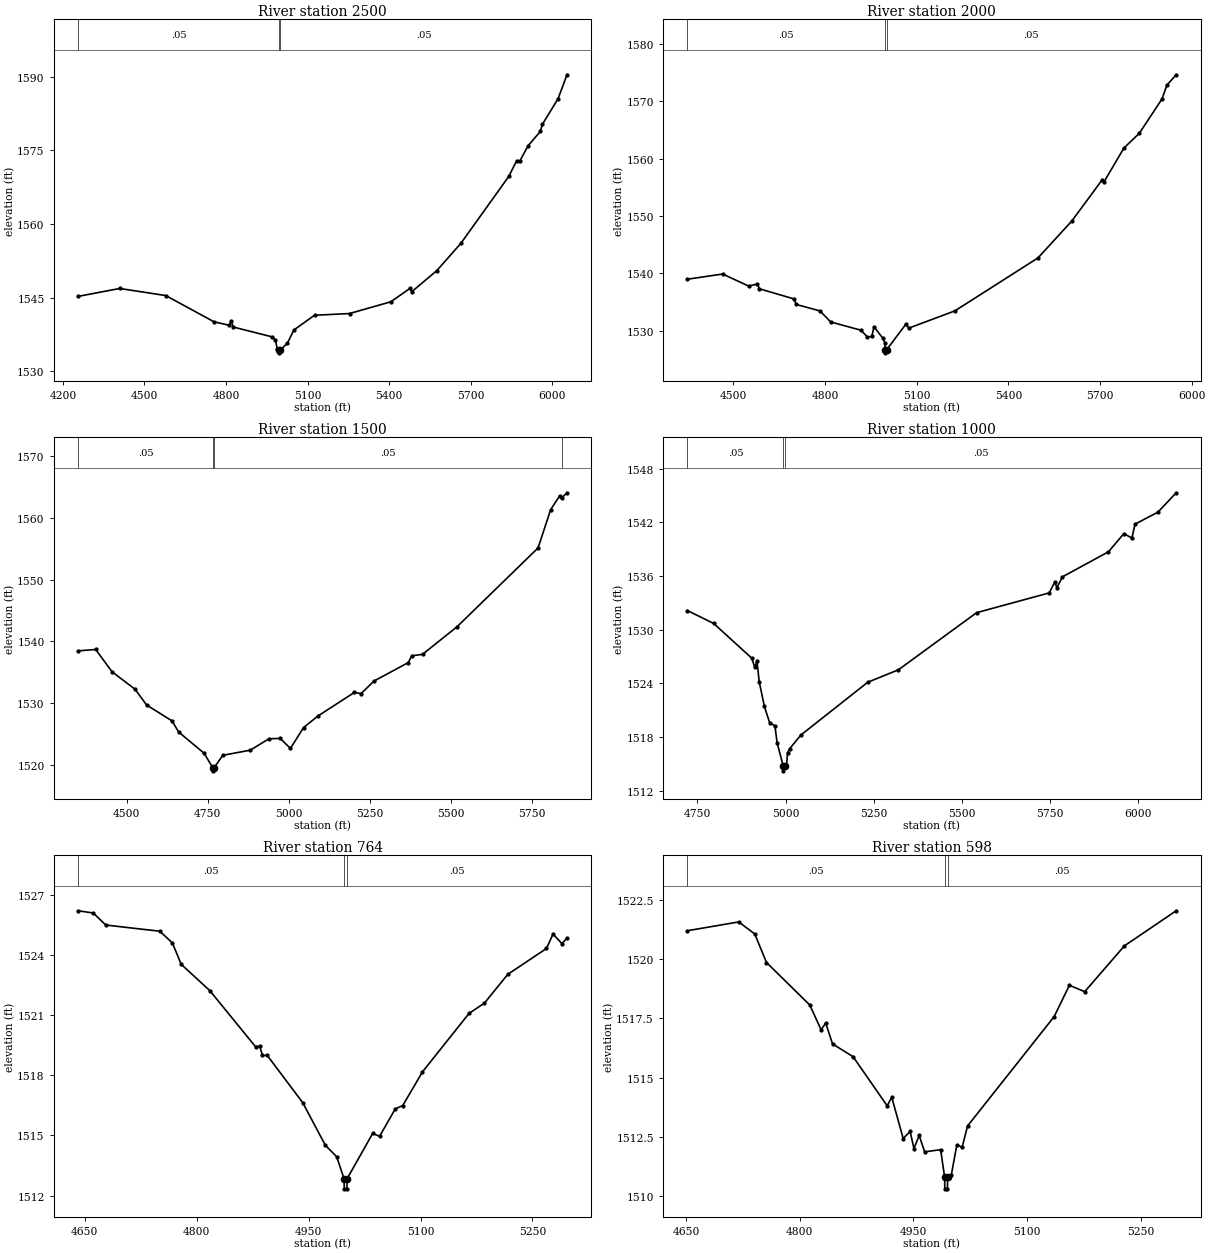
Type RM Length L Ch R = 1,2500,500,500,500
BEGIN DESCRIPTION:
HICKORY25 5.0
END DESCRIPTION:
XS GIS Cut Line= 3
      2756056.43     10168968.52      2755520.58     10169483.94
      2755105.70     10170453.07
#Sta/Elev= 30
  4256.5 1545.29  4408.9 1546.89  4578.4 1545.45  4755.4 1540.12  4812.0 1539.40
  4819.0 1540.31  4826.2 1539.05  4967.4 1537.07  4981.6 1536.45  4988.8 1534.48
  4993.7 1534.29  4994.0 1533.79  4997.7 1534.29  5025.7 1535.72  5049.3 1538.43
  5125.5 1541.44  5254.3 1541.79  5406.7 1544.19  5477.4 1546.94  5482.8 1546.21
  5575.6 1550.54  5664.2 1556.10  5840.2 1569.71  5869.3 1572.93  5880.2 1572.77
  5910.9 1575.93  5956.3 1578.86  5963.5 1580.28  6021.6 1585.54  6054.2 1590.39
#Mann=3,-1,0
  4256.5    0.05       0  4993.7    0.05       0  4997.7    0.05       0
Bank Sta=4993.7,4997.7
Exp/Cntr=0.3,0.1

Type RM Length L Ch R = 1,2000,500,500,500
BEGIN DESCRIPTION:
HICKORY25 4.0
END DESCRIPTION:
XS GIS Cut Line= 3
      2755499.55     10168884.14      2755055.64     10169359.09
      2754955.68     10170303.11
#Sta/Elev= 30
  4349.9 1538.96  4465.1 1539.86  4550.1 1537.76  4578.4 1538.13  4585.3 1537.29
  4698.6 1535.52  4705.5 1534.56  4783.6 1533.43  4818.8 1531.50  4918.0 1530.06
  4939.0 1528.86  4953.1 1528.99  4960.5 1530.66  4988.8 1528.70  4995.6 1527.91
  4997.3 1526.62  4997.6 1526.12  5001.3 1526.62  5064.4 1531.10  5074.4 1530.43
  5225.3 1533.44  5496.8 1542.66  5607.4 1549.08  5707.4 1556.30  5712.4 1555.86
  5778.3 1561.83  5828.6 1564.39  5902.9 1570.37  5919.1 1572.81  5949.3 1574.60
#Mann=3,-1,0
  4349.9    0.05       0  4997.3    0.05       0  5001.3    0.05       0
Bank Sta=4997.3,5001.3
Exp/Cntr=0.3,0.1

Type RM Length L Ch R = 1,1500,500,500,500
BEGIN DESCRIPTION:
HICKORY25 3.0
END DESCRIPTION:
XS GIS Cut Line= 3
      2755050.63     10168671.69      2754644.64     10169178.79
      2754405.67     10170003.15
#Sta/Elev= 30
  4350.4 1538.46  4404.1 1538.68  4454.7 1535.06  4525.7 1532.23  4561.0 1529.69
  4639.4 1527.11  4660.2 1525.30  4738.6 1521.86  4765.4 1519.51  4765.7 1519.01
  4769.4 1519.51  4796.3 1521.53  4881.1 1522.36  4938.7 1524.21  4973.9 1524.26
  5004.9 1522.64  5045.5 1526.03  5089.5 1527.88  5202.3 1531.72  5223.1 1531.53
  5262.6 1533.56  5368.5 1536.55  5379.3 1537.66  5412.5 1537.89  5518.5 1542.34
  5769.1 1555.14  5807.9 1561.34  5836.3 1563.63  5841.4 1563.21  5858.3 1564.08
#Mann=4,-1,0
  4350.4    0.05       0  4765.4    0.05       0  4769.4    0.05       0
  5841.4    0.12       0
Bank Sta=4765.4,4769.4
Exp/Cntr=0.3,0.1

Type RM Length L Ch R = 1,1000,236,236,236
BEGIN DESCRIPTION:
HICKORY25 2.0
END DESCRIPTION:
XS GIS Cut Line= 3
      2754824.96     10168578.57      2754593.53     10168733.33
      2754055.71     10169703.07
#Sta/Elev= 30
  4721.6 1532.14  4795.8 1530.71  4903.9 1526.83  4912.9 1525.78  4918.9 1526.50
  4925.2 1524.20  4940.0 1521.42  4955.0 1519.59  4970.0 1519.24  4976.0 1517.37
  4993.7 1514.72  4993.9 1514.22  4997.7 1514.72  5002.7 1514.72  5005.7 1516.22
  5011.4 1516.68  5043.4 1518.22  5233.4 1524.13  5320.4 1525.52  5542.4 1531.91
  5748.4 1534.12  5764.5 1535.34  5770.2 1534.70  5786.2 1535.92  5916.7 1538.72
  5960.3 1540.75  5983.2 1540.26  5992.2 1541.81  6057.4 1543.16  6108.9 1545.32
#Mann=3,-1,0
  4721.6    0.05       0  4993.7    0.05       0  4997.7    0.05       0
Bank Sta=4993.7,4997.7
Exp/Cntr=0.3,0.1

Type RM Length L Ch R = 1,764,166,166,166
BEGIN DESCRIPTION:
Mapping XS 980a2216
END DESCRIPTION:
XS GIS Cut Line= 4
      2754649.01     10168469.31      2754426.37     10168581.28
      2754326.11     10168737.53      2754266.63     10168949.59
#Sta/Elev= 30
  4641.2 1526.20  4661.3 1526.09  4678.0 1525.49  4750.5 1525.18  4767.3 1524.60
  4779.2 1523.53  4817.5 1522.22  4878.9 1519.42  4884.5 1519.45  4888.0 1518.99
  4894.5 1518.99  4942.0 1516.64  4972.4 1514.51  4987.6 1513.94  4997.5 1512.84
  4997.8 1512.34  5001.3 1512.34  5001.5 1512.84  5035.8 1515.10  5045.1 1514.96
  5066.2 1516.33  5076.1 1516.49  5102.6 1518.17  5164.9 1521.08  5185.7 1521.60
  5216.9 1523.03  5268.8 1524.32  5277.6 1525.04  5289.6 1524.56  5296.3 1524.84
#Mann=3,-1,0
  4641.2    0.05       0  4997.5    0.05       0  5001.5    0.05       0
Bank Sta=4997.5,5001.5
Exp/Cntr=0.3,0.1

Type RM Length L Ch R = 1,598,375,375,375
BEGIN DESCRIPTION:
Mapping XS af1311da
END DESCRIPTION:
XS GIS Cut Line= 5
      2754538.35     10168362.54      2754448.51     10168418.52
      2754292.26     10168522.69      2754201.11     10168609.93
      2754171.16     10168832.61
#Sta/Elev= 30
  4652.0 1521.19  4719.6 1521.56  4740.8 1521.05  4756.2 1519.85  4813.3 1518.06
  4828.3 1517.01  4834.3 1517.30  4843.3 1516.42  4870.4 1515.88  4915.4 1513.81
  4921.4 1514.17  4936.5 1512.43  4945.6 1512.73  4950.7 1512.01  4957.6 1512.56
  4964.8 1511.87  4985.9 1511.96  4991.1 1510.81  4991.4 1510.31  4994.9 1510.31
  4995.1 1510.81  5000.0 1510.90  5007.3 1512.17  5014.2 1512.06  5021.4 1512.96
  5135.6 1517.57  5155.7 1518.89  5175.9 1518.62  5228.2 1520.55  5296.5 1522.03
#Mann=3,-1,0
  4652.0    0.05       0  4991.1    0.05       0  4995.1    0.05       0
Bank Sta=4991.1,4995.1
Exp/Cntr=0.3,0.1

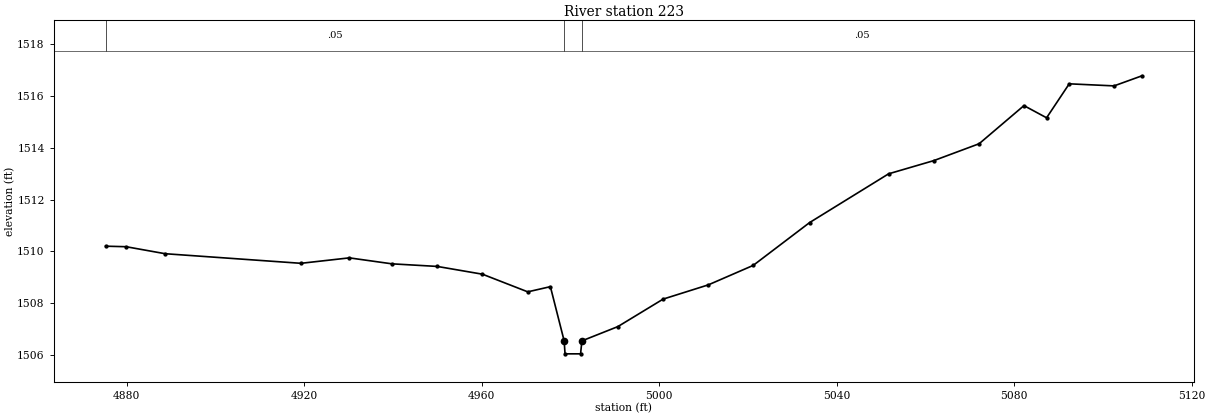
Type RM Length L Ch R = 1,223,0,0,0
BEGIN DESCRIPTION:
HICKORY25 1.0
END DESCRIPTION:
XS GIS Cut Line= 3
      2754100.86     10168329.97      2754080.68     10168428.11
      2754104.54     10168559.26
#Sta/Elev= 27
  4875.3 1510.20  4879.9 1510.18  4888.7 1509.91  4919.3 1509.54  4930.2 1509.75
  4939.8 1509.52  4950.0 1509.42  4960.2 1509.12  4970.4 1508.44  4975.5 1508.64
  4978.6 1506.55  4978.8 1506.05  4982.3 1506.05  4982.6 1506.55  4990.7 1507.10
  5000.9 1508.16  5011.1 1508.71  5021.2 1509.46  5033.9 1511.11  5051.7 1512.99
  5061.9 1513.50  5072.1 1514.15  5082.2 1515.62  5087.3 1515.15  5092.4 1516.46
  5102.5 1516.38  5108.8 1516.77
#Mann=3,-1,0
  4875.3    0.05       0  4978.6    0.05       0  4982.6    0.05       0
Bank Sta=4978.6,4982.6
Exp/Cntr=0.3,0.1

Chan Stop Cuts=-1