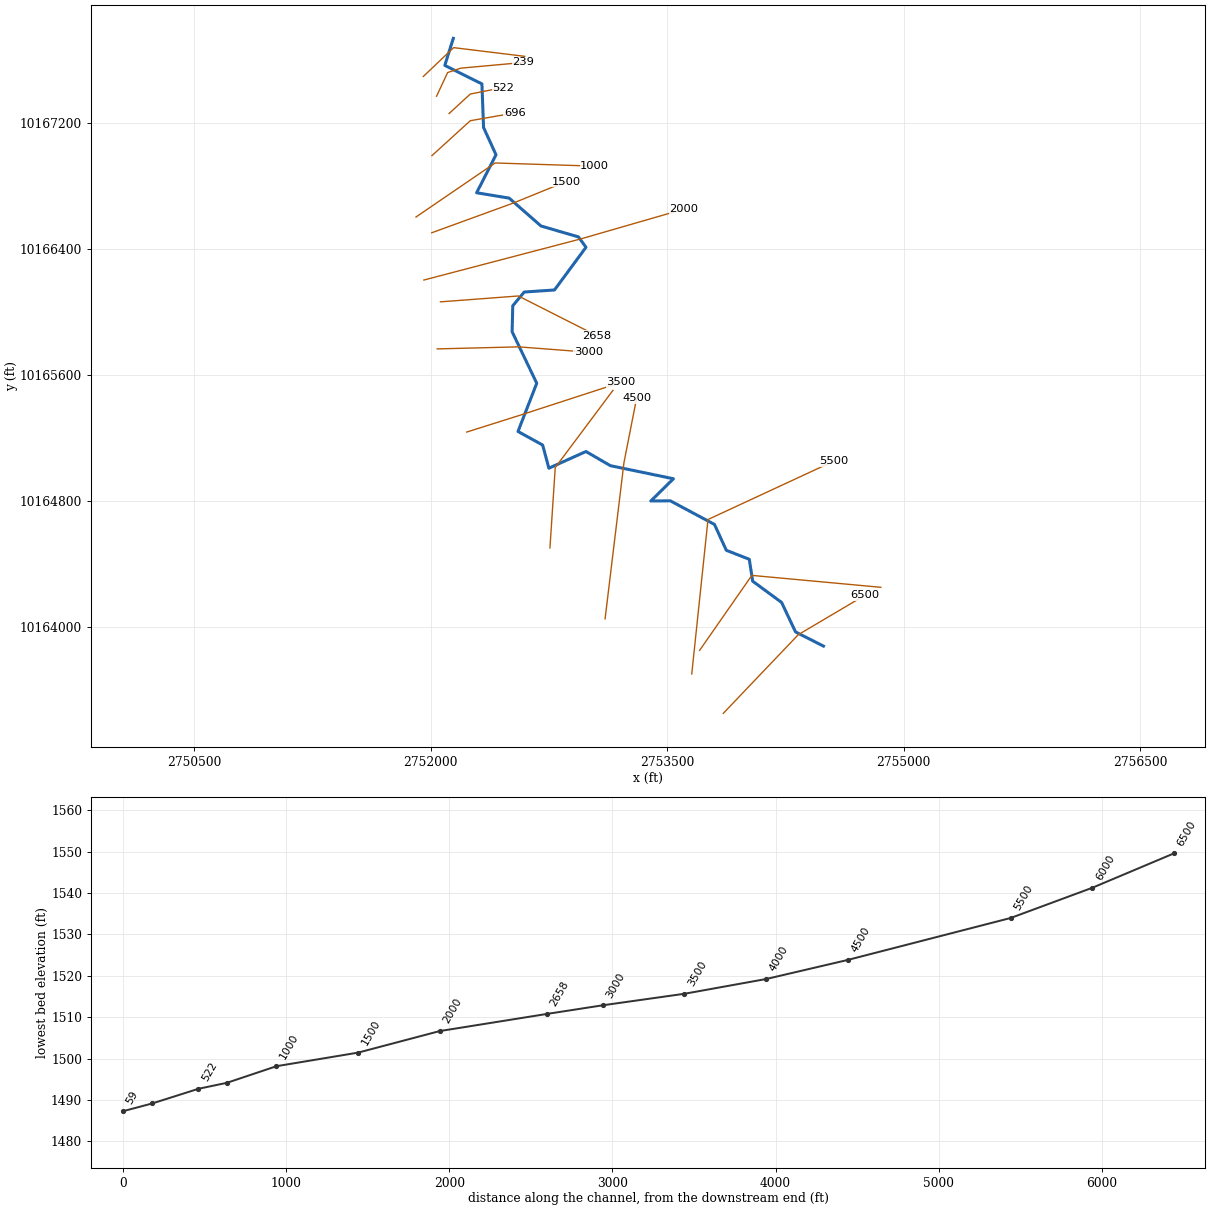
--- HICKORY26.prj (project) ---

Proj Title=HICKORY26 Base Level Engineering
Current Plan=p01
Default Exp/Contr=0.3,0.1
English Units
Geom File=g01
Flow File=f01
Plan File=p01
BEGIN DESCRIPTION:
HICKORY26
END DESCRIPTION:

--- HICKORY26.p01 (plan) ---

Plan Title=Multiple Run
Short Identifier=Multiple
Geom File=g01
Flow File=f01
Subcritical Flow
K Sum by GR= 0
Std Step Tol= 0.01
Critical Tol= 0.01
Num of Std Step Trials= 20
Max Error Tol= 0.3
Flow Tol Ratio= 0.001
Split Flow NTrial= 30
Split Flow Tol= 0.02
Split Flow Ratio= 0.02
Log Output Level= 0
Friction Slope Method= 1
Unsteady Friction Slope Method= 2
Unsteady Bridges Friction Slope Method= 1
Parabolic Critical Depth
Global Vel Dist=  1 , 1 , 1
Global Log Level= 0
CheckData=True
Encroach Param= -1, 0, 0, 0
BEGIN DESCRIPTION:
Multiple Run
END DESCRIPTION:

--- HICKORY26.f01 (steady flow) ---

Flow Title=Multiple
Number of Profiles=7
Profile Names=10-year,25-year,50-year,1pct_min,100-year,1pct_plu,500-year
River Rch & RM= HICKORY26,Reach-1,6500
     458     748    1220     908    1676    3093    2383
Boundary for River Rch & Prof#=HICKORY26,Reach-1,1
Up Type=0
Dn Type=3
Dn Slope=0.005
Boundary for River Rch & Prof#=HICKORY26,Reach-1,2
Up Type=0
Dn Type=3
Dn Slope=0.005
Boundary for River Rch & Prof#=HICKORY26,Reach-1,3
Up Type=0
Dn Type=3
Dn Slope=0.005
Boundary for River Rch & Prof#=HICKORY26,Reach-1,4
Up Type=0
Dn Type=3
Dn Slope=0.005
Boundary for River Rch & Prof#=HICKORY26,Reach-1,5
Up Type=0
Dn Type=3
Dn Slope=0.005
Boundary for River Rch & Prof#=HICKORY26,Reach-1,6
Up Type=0
Dn Type=3
Dn Slope=0.005
Boundary for River Rch & Prof#=HICKORY26,Reach-1,7
Up Type=0
Dn Type=3
Dn Slope=0.005

--- HICKORY26.g01 (geometry) ---

Geom Title=Existing Conditions

River Reach=HICKORY26,Reach-1
Reach XY= 30
      2754491.50     10163880.00      2754314.25     10163970.00
      2754226.00     10164157.00      2754042.25     10164292.00
      2754020.75     10164431.00      2753875.00     10164488.00
      2753800.00     10164652.00      2753519.75     10164802.00
      2753396.00     10164801.00      2753539.50     10164942.00
      2753139.50     10165025.00      2752984.25     10165115.00
      2752749.00     10165009.00      2752709.50     10165156.00
      2752553.00     10165242.00      2752672.00     10165548.00
      2752515.75     10165875.00      2752519.75     10166040.00
      2752592.75     10166127.00      2752784.50     10166140.00
      2752984.50     10166411.00      2752936.50     10166477.00
      2752699.00     10166546.00      2752497.00     10166723.00
      2752290.50     10166757.00      2752413.50     10166998.00
      2752334.50     10167171.00      2752324.00     10167448.00
      2752088.50     10167565.00      2752142.50     10167737.00

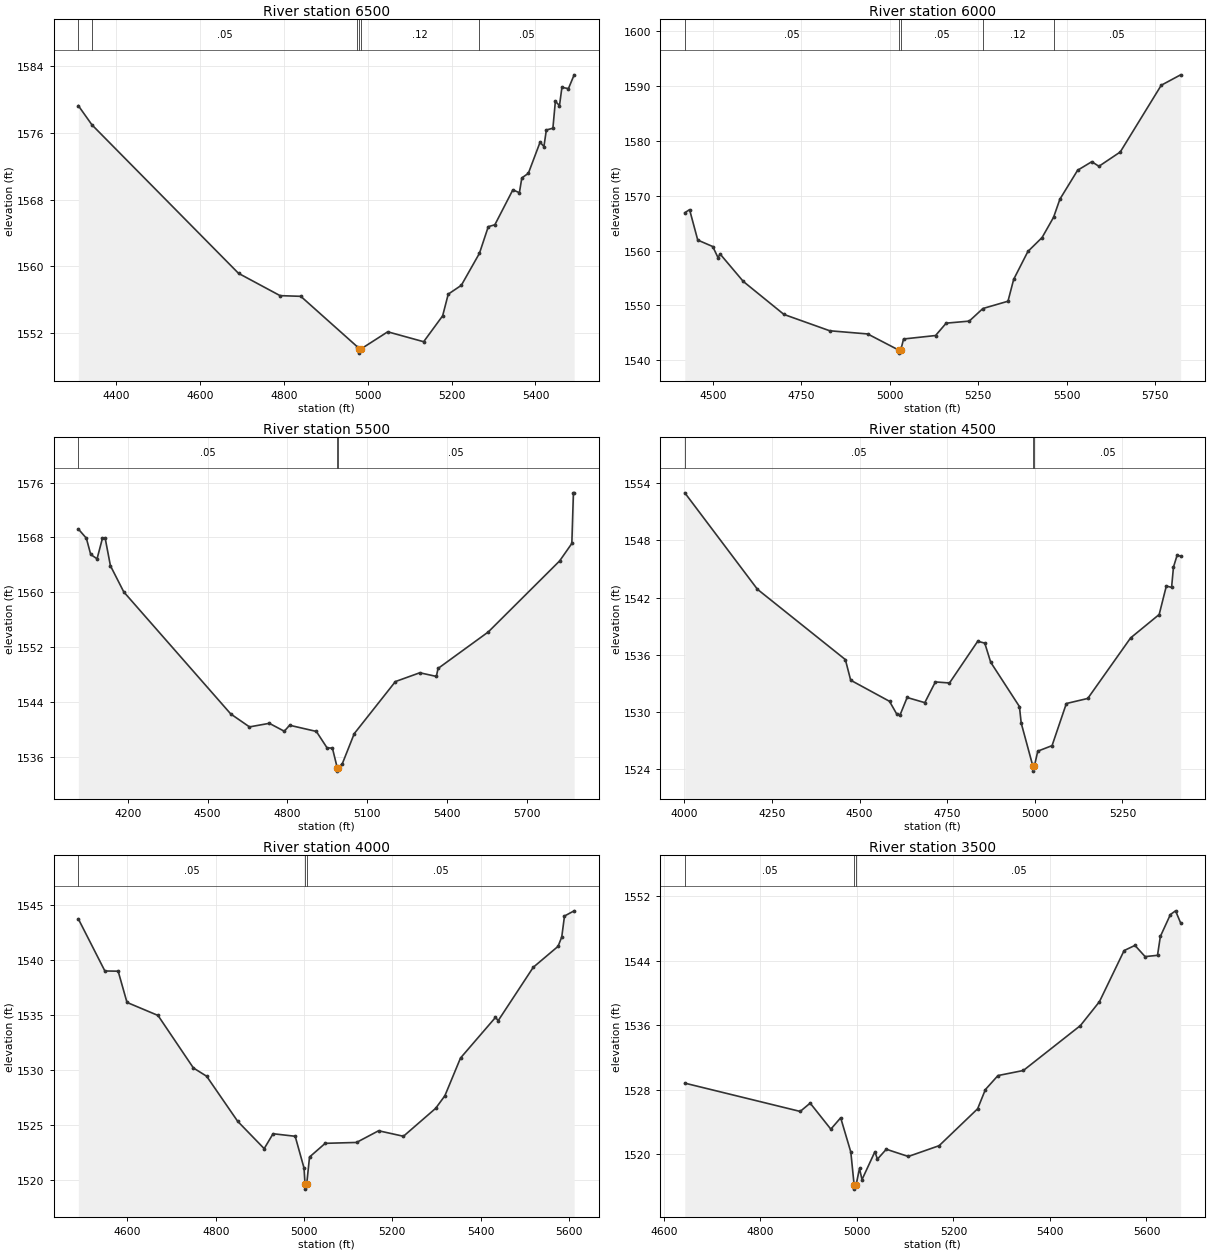
Type RM Length L Ch R = 1,6500,500,500,500
BEGIN DESCRIPTION:
HICKORY26 12.0
END DESCRIPTION:
XS GIS Cut Line= 3
      2753855.65     10163453.08      2754331.97     10163952.57
      2754755.65     10164203.09
#Sta/Elev= 30
  4309.8 1579.30  4342.2 1577.00  4691.8 1559.17  4790.9 1556.49  4840.3 1556.41
  4974.5 1550.38  4979.8 1550.09  4980.1 1549.59  4983.8 1550.09  5047.6 1552.15
  5133.3 1550.96  5178.6 1554.07  5191.9 1556.67  5223.1 1557.73  5266.3 1561.57
  5287.4 1564.77  5303.1 1565.00  5346.0 1569.19  5361.6 1568.85  5367.4 1570.62
  5383.0 1571.18  5410.9 1574.91  5420.1 1574.39  5425.9 1576.38  5441.5 1576.59
  5447.4 1579.82  5457.2 1579.30  5463.0 1581.49  5478.6 1581.35  5492.2 1583.00
#Mann=6,-1,0
  4309.8    0.12       0  4342.2    0.05       0  4974.5    0.12       0
  4979.8    0.07       0  4983.8    0.12       0  5266.3    0.05       0
Bank Sta=4979.8,4983.8
Exp/Cntr=0.3,0.1

Type RM Length L Ch R = 1,6000,500,500,500
BEGIN DESCRIPTION:
HICKORY26 11.0
END DESCRIPTION:
XS GIS Cut Line= 3
      2753705.68     10163853.11      2754037.07     10164328.75
      2754855.68     10164253.11
#Sta/Elev= 30
  4420.3 1566.90  4433.8 1567.46  4456.9 1561.91  4499.3 1560.73  4514.1 1558.72
  4520.2 1559.36  4585.7 1554.36  4700.6 1548.34  4830.0 1545.36  4937.3 1544.78
  5026.7 1541.78  5027.0 1541.28  5030.7 1541.78  5038.8 1543.86  5129.2 1544.49
  5159.3 1546.75  5224.4 1547.12  5263.1 1549.42  5334.0 1550.75  5350.1 1554.74
  5390.3 1559.83  5430.4 1562.37  5463.0 1566.08  5480.7 1569.36  5530.9 1574.65
  5571.0 1576.21  5591.1 1575.37  5651.4 1577.98  5767.3 1590.16  5822.1 1592.06
#Mann=5,-1,0
  4420.3    0.05       0  5026.7    0.05       0  5030.7    0.05       0
  5263.1    0.12       0  5463.0    0.05       0
Bank Sta=5026.7,5030.7
Exp/Cntr=0.3,0.1

Type RM Length L Ch R = 1,5500,1000,1000,1000
BEGIN DESCRIPTION:
HICKORY26 10.0
END DESCRIPTION:
XS GIS Cut Line= 3
      2753655.68     10163703.10      2753758.77     10164683.39
      2754555.68     10165053.11
#Sta/Elev= 30
  4014.3 1569.23  4044.5 1567.89  4060.8 1565.53  4084.7 1564.89  4104.8 1567.86
  4114.9 1567.96  4135.0 1563.88  4185.2 1560.07  4587.5 1542.30  4657.8 1540.42
  4732.4 1540.94  4788.6 1539.79  4808.7 1540.66  4909.2 1539.76  4949.4 1537.37
  4969.6 1537.33  4987.7 1534.48  4987.9 1533.98  4991.7 1534.48  5006.7 1535.05
  5051.7 1539.44  5206.4 1547.02  5298.1 1548.30  5360.4 1547.77  5366.8 1548.93
  5555.5 1554.24  5824.0 1564.59  5869.8 1567.13  5875.7 1574.50  5878.5 1574.50
#Mann=3,-1,0
  4014.3    0.05       0  4987.7    0.03       0  4991.7    0.05       0
Bank Sta=4987.7,4991.7
Exp/Cntr=0.3,0.1

Type RM Length L Ch R = 1,4500,500,500,500
BEGIN DESCRIPTION:
HICKORY26 9.0
END DESCRIPTION:
XS GIS Cut Line= 3
      2753105.69     10164053.16      2753225.58     10165044.84
      2753305.69     10165453.15
#Sta/Elev= 30
  4001.1 1552.96  4208.4 1542.86  4459.3 1535.50  4474.5 1533.34  4585.3 1531.13
  4605.4 1529.83  4615.5 1529.71  4635.6 1531.53  4686.0 1530.99  4716.2 1533.16
  4756.5 1533.05  4837.1 1537.42  4857.2 1537.22  4874.1 1535.22  4956.1 1530.58
  4961.1 1528.86  4994.6 1524.32  4994.9 1523.82  4998.6 1524.32  5008.4 1525.91
  5049.2 1526.49  5090.0 1530.90  5151.1 1531.43  5273.4 1537.77  5354.9 1540.22
  5375.3 1543.20  5390.3 1543.06  5395.7 1545.19  5405.9 1546.40  5416.1 1546.34
#Mann=3,-1,0
  4001.1    0.05       0  4994.6    0.05       0  4998.6    0.05       0
Bank Sta=4994.6,4998.6
Exp/Cntr=0.3,0.1

Type RM Length L Ch R = 1,4000,500,500,500
BEGIN DESCRIPTION:
HICKORY26 8.0
END DESCRIPTION:
XS GIS Cut Line= 3
      2752755.68     10164503.10      2752789.41     10165013.19
      2753155.68     10165503.11
#Sta/Elev= 30
  4488.8 1543.70  4548.9 1538.98  4579.0 1538.96  4599.0 1536.13  4669.2 1534.95
  4749.4 1530.19  4779.4 1529.44  4849.6 1525.36  4909.7 1522.88  4929.8 1524.23
  4979.9 1524.00  5000.0 1521.11  5002.1 1519.71  5002.4 1519.21  5006.1 1519.71
  5012.4 1522.12  5047.9 1523.36  5118.8 1523.44  5168.8 1524.50  5225.1 1524.00
  5298.0 1526.53  5318.9 1527.67  5354.3 1531.09  5433.5 1534.77  5439.7 1534.48
  5519.0 1539.31  5575.2 1541.21  5583.6 1542.06  5589.8 1543.96  5611.7 1544.43
#Mann=3,-1,0
  4488.8    0.05       0  5002.1    0.05       0  5006.1    0.05       0
Bank Sta=5002.1,5006.1
Exp/Cntr=0.3,0.1

Type RM Length L Ch R = 1,3500,500,500,500
BEGIN DESCRIPTION:
HICKORY26 7.0
END DESCRIPTION:
XS GIS Cut Line= 3
      2752227.69     10165238.32      2752567.72     10165345.76
      2753205.67     10165553.11
#Sta/Elev= 30
  4643.4 1528.80  4882.5 1525.29  4903.2 1526.32  4946.0 1523.09  4966.4 1524.50
  4987.4 1520.25  4994.3 1516.15  4994.6 1515.65  4998.3 1516.15  5005.4 1518.22
  5010.6 1516.83  5037.3 1520.29  5042.6 1519.37  5060.9 1520.60  5106.5 1519.70
  5170.4 1521.04  5250.2 1525.62  5266.2 1528.00  5292.3 1529.74  5344.9 1530.37
  5463.1 1535.94  5502.6 1538.91  5553.7 1545.25  5576.2 1545.89  5597.2 1544.50
  5622.9 1544.66  5628.8 1547.00  5649.6 1549.72  5660.3 1550.18  5670.8 1548.68
#Mann=3,-1,0
  4643.4    0.05       0  4994.3    0.03       0  4998.3    0.05       0
Bank Sta=4994.3,4998.3
Exp/Cntr=0.3,0.1

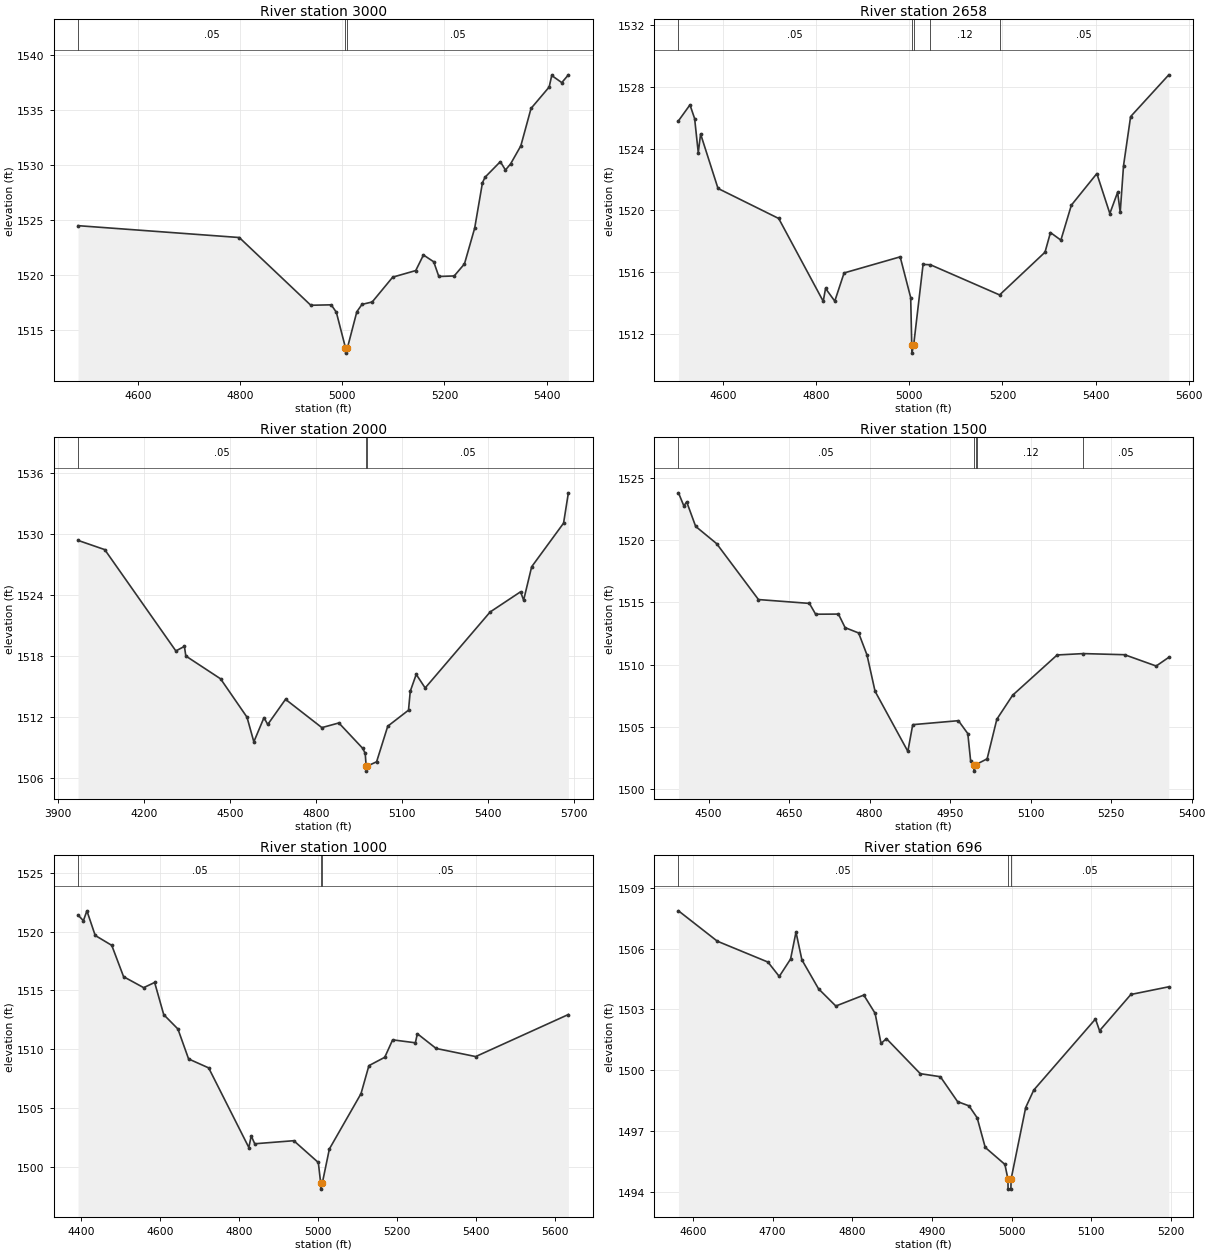
Type RM Length L Ch R = 1,3000,342,342,342
BEGIN DESCRIPTION:
HICKORY26 6.0
END DESCRIPTION:
XS GIS Cut Line= 3
      2752040.20     10165766.10      2752557.23     10165779.10
      2752998.54     10165745.26
#Sta/Elev= 30
  4482.8 1524.48  4798.4 1523.40  4938.4 1517.23  4978.4 1517.27  4988.4 1516.59
  5006.2 1513.37  5006.5 1512.87  5010.2 1513.37  5028.5 1516.64  5038.6 1517.31
  5058.6 1517.53  5098.7 1519.79  5143.8 1520.39  5158.9 1521.81  5179.0 1521.19
  5189.0 1519.85  5219.1 1519.90  5239.2 1521.00  5259.2 1524.26  5274.4 1528.39
  5279.4 1528.89  5309.4 1530.31  5319.4 1529.55  5329.4 1530.10  5349.5 1531.75
  5369.5 1535.16  5405.0 1537.11  5410.0 1538.16  5429.7 1537.51  5442.6 1538.22
#Mann=3,-1,0
  4482.8    0.05       0  5006.2    0.05       0  5010.2    0.05       0
Bank Sta=5006.2,5010.2
Exp/Cntr=0.3,0.1

Type RM Length L Ch R = 1,2658,658,658,658
BEGIN DESCRIPTION:
HICKORY26 5.0
END DESCRIPTION:
XS GIS Cut Line= 3
      2752061.05     10166064.71      2752555.25     10166102.00
      2753052.36     10165850.30
#Sta/Elev= 30
  4504.4 1525.79  4529.1 1526.82  4539.1 1525.93  4546.9 1523.73  4551.9 1524.94
  4589.3 1521.42  4719.6 1519.48  4815.2 1514.13  4820.2 1514.96  4840.0 1514.14
  4860.0 1515.96  4980.4 1517.00  5003.0 1514.37  5005.3 1511.28  5005.6 1510.78
  5009.3 1511.28  5029.6 1516.51  5045.3 1516.49  5193.9 1514.54  5291.4 1517.30
  5303.1 1518.57  5325.5 1518.08  5348.0 1520.34  5402.7 1522.38  5430.6 1519.80
  5447.3 1521.17  5452.9 1519.88  5460.0 1522.89  5475.2 1526.06  5557.2 1528.76
#Mann=5,-1,0
  4504.4    0.05       0  5005.3    0.05       0  5009.3    0.05       0
  5045.3    0.12       0  5193.9    0.05       0
Bank Sta=5005.3,5009.3
Exp/Cntr=0.3,0.1

Type RM Length L Ch R = 1,2000,500,500,500
BEGIN DESCRIPTION:
HICKORY26 4.0
END DESCRIPTION:
XS GIS Cut Line= 3
      2751955.65     10166203.10      2752951.31     10166464.08
      2753605.66     10166653.10
#Sta/Elev= 30
  3970.7 1529.38  4063.8 1528.47  4311.9 1518.48  4341.6 1518.93  4346.7 1517.98
  4467.9 1515.73  4560.0 1511.95  4583.9 1509.52  4619.2 1511.90  4632.4 1511.23
  4694.4 1513.71  4821.2 1510.92  4880.5 1511.38  4963.2 1508.89  4972.4 1508.39
  4975.6 1507.13  4975.8 1506.63  4979.6 1507.13  5012.1 1507.55  5051.0 1511.06
  5123.4 1512.64  5129.5 1514.50  5150.3 1516.17  5181.5 1514.83  5408.1 1522.32
  5514.2 1524.31  5525.0 1523.49  5553.0 1526.78  5664.3 1531.08  5681.1 1534.07
#Mann=3,-1,0
  3970.7    0.05       0  4975.6    0.03       0  4979.6    0.05       0
Bank Sta=4975.6,4979.6
Exp/Cntr=0.3,0.1

Type RM Length L Ch R = 1,1500,500,500,500
BEGIN DESCRIPTION:
HICKORY26 3.0
END DESCRIPTION:
XS GIS Cut Line= 3
      2752005.66     10166503.10      2752528.07     10166693.43
      2752859.03     10166828.35
#Sta/Elev= 30
  4444.0 1523.82  4454.0 1522.77  4459.3 1523.09  4476.0 1521.12  4515.1 1519.73
  4593.0 1515.23  4687.9 1514.92  4699.5 1514.05  4742.0 1514.06  4754.4 1512.97
  4779.6 1512.54  4795.2 1510.77  4810.2 1507.85  4871.3 1503.01  4880.4 1505.16
  4965.5 1505.48  4983.0 1504.44  4988.3 1502.22  4994.1 1501.92  4994.3 1501.42
  4998.1 1501.92  5001.0 1502.01  5019.0 1502.41  5037.1 1505.60  5066.5 1507.53
  5149.4 1510.77  5198.2 1510.88  5275.1 1510.79  5333.9 1509.88  5357.4 1510.58
#Mann=5,-1,0
  4444.0    0.05       0  4994.1    0.05       0  4998.1    0.05       0
  5001.0    0.12       0  5198.2    0.05       0
Bank Sta=4994.1,4998.1
Exp/Cntr=0.3,0.1

Type RM Length L Ch R = 1,1000,304,304,304
BEGIN DESCRIPTION:
HICKORY26 2.0
END DESCRIPTION:
XS GIS Cut Line= 3
      2751905.66     10166603.09      2752407.70     10166946.04
      2753040.18     10166925.82
#Sta/Elev= 30
  4392.0 1521.40  4405.5 1520.92  4414.4 1521.76  4435.4 1519.67  4477.3 1518.83
  4507.2 1516.17  4558.0 1515.24  4585.8 1515.68  4608.8 1512.95  4644.7 1511.73
  4671.7 1509.19  4722.5 1508.43  4824.2 1501.67  4830.2 1502.66  4839.1 1501.99
  4937.9 1502.25  5000.0 1500.40  5006.0 1498.64  5006.2 1498.14  5010.0 1498.64
  5028.0 1501.55  5108.0 1506.24  5128.0 1508.62  5168.1 1509.33  5188.1 1510.81
  5245.6 1510.56  5250.6 1511.33  5298.1 1510.08  5398.2 1509.39  5632.8 1512.96
#Mann=3,-1,0
  4392.0    0.05       0  5006.0    0.05       0  5010.0    0.05       0
Bank Sta=5006,5010
Exp/Cntr=0.3,0.1

Type RM Length L Ch R = 1,696,174,174,174
BEGIN DESCRIPTION:
Mapping XS d9b8a5a8
END DESCRIPTION:
XS GIS Cut Line= 3
      2752007.20     10166992.88      2752250.25     10167214.23
      2752532.59     10167263.80
#Sta/Elev= 30
  4581.9 1507.86  4630.7 1506.36  4694.2 1505.33  4708.4 1504.62  4722.6 1505.48
  4729.4 1506.81  4736.8 1505.44  4757.7 1504.01  4779.4 1503.16  4814.5 1503.70
  4828.7 1502.80  4836.1 1501.31  4842.9 1501.55  4885.4 1499.82  4910.6 1499.67
  4932.2 1498.44  4946.6 1498.23  4956.8 1497.64  4966.9 1496.18  4991.6 1495.34
  4995.4 1494.62  4995.6 1494.12  4999.1 1494.12  4999.4 1494.62  5017.7 1498.15
  5027.8 1499.01  5105.3 1502.52  5110.4 1501.94  5149.7 1503.73  5197.3 1504.11
#Mann=3,-1,0
  4581.9    0.05       0  4995.4    0.05       0  4999.4    0.05       0
Bank Sta=4995.4,4999.4
Exp/Cntr=0.3,0.1

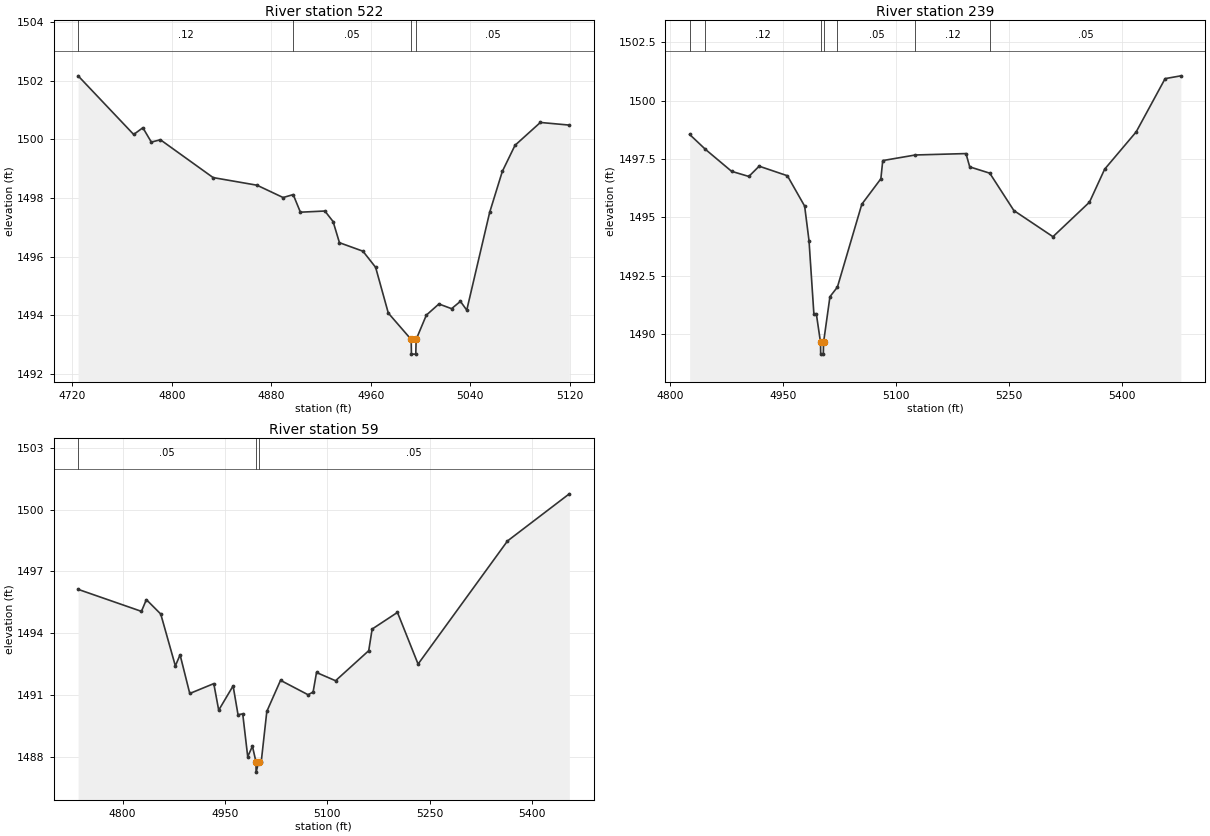
Type RM Length L Ch R = 1,522,283,283,283
BEGIN DESCRIPTION:
Mapping XS d25ce2b0
END DESCRIPTION:
XS GIS Cut Line= 3
      2752115.70     10167259.80      2752250.25     10167383.50
      2752458.54     10167424.73
#Sta/Elev= 30
  4724.7 1502.17  4769.4 1500.17  4776.8 1500.40  4783.6 1499.91  4790.9 1499.99
  4833.3 1498.70  4868.6 1498.44  4889.6 1498.02  4897.7 1498.12  4903.5 1497.52
  4923.2 1497.56  4929.8 1497.20  4934.9 1496.48  4953.8 1496.19  4964.0 1495.64
  4974.2 1494.08  4992.6 1493.18  4992.8 1492.68  4996.3 1492.68  4996.6 1493.18
  5004.8 1494.01  5014.9 1494.39  5025.1 1494.23  5032.2 1494.48  5037.3 1494.18
  5055.7 1497.51  5065.9 1498.91  5076.1 1499.80  5096.5 1500.58  5119.8 1500.49
#Mann=4,-1,0
  4724.7    0.12       0  4897.7    0.05       0  4992.6    0.05       0
  4996.6    0.05       0
Bank Sta=4992.6,4996.6
Exp/Cntr=0.3,0.1

Type RM Length L Ch R = 1,239,180,180,180
BEGIN DESCRIPTION:
Mapping XS 7950491a
END DESCRIPTION:
XS GIS Cut Line= 4
      2752036.23     10167369.52      2752106.47     10167519.97
      2752189.80     10167547.74      2752586.49     10167583.77
#Sta/Elev= 30
  4826.4 1498.55  4847.4 1497.91  4882.1 1496.97  4905.0 1496.75  4918.7 1497.19
  4956.2 1496.78  4979.1 1495.48  4984.9 1494.00  4991.4 1490.85  4994.7 1490.85
  5000.2 1489.64  5000.4 1489.14  5003.9 1489.14  5004.2 1489.64  5012.7 1491.60
  5022.6 1492.01  5055.0 1495.56  5080.3 1496.65  5082.8 1497.43  5126.1 1497.67
  5193.3 1497.73  5198.3 1497.16  5224.9 1496.89  5256.9 1495.29  5308.8 1494.17
  5357.3 1495.65  5377.4 1497.06  5419.3 1498.66  5457.7 1500.94  5478.6 1501.06
#Mann=7,-1,0
  4826.4    0.05       0  4847.4    0.12       0  5000.2    0.07       0
  5004.2    0.12       0  5022.6    0.05       0  5126.1    0.12       0
  5224.9    0.05       0
Bank Sta=5000.2,5004.2
Exp/Cntr=0.3,0.1

Type RM Length L Ch R = 1,59,0,0,0
BEGIN DESCRIPTION:
HICKORY26 1.0
END DESCRIPTION:
XS GIS Cut Line= 3
      2751952.36     10167495.20      2752144.50     10167678.00
      2752595.64     10167622.83
#Sta/Elev= 30
  4734.8 1496.13  4827.6 1495.06  4834.8 1495.63  4855.9 1494.93  4877.3 1492.41
  4884.2 1492.95  4898.4 1491.07  4933.6 1491.55  4940.8 1490.26  4961.9 1491.44
  4969.1 1490.04  4976.0 1490.08  4983.3 1488.00  4990.2 1488.51  4995.4 1487.75
  4995.6 1487.25  4999.4 1487.75  5003.1 1487.75  5011.3 1490.20  5031.4 1491.71
  5071.7 1491.01  5079.1 1491.14  5084.1 1492.09  5112.0 1491.69  5160.6 1493.15
  5165.6 1494.20  5202.7 1495.01  5232.9 1492.50  5363.9 1498.48  5454.5 1500.77
#Mann=3,-1,0
  4734.8    0.05       0  4995.4    0.05       0  4999.4    0.05       0
Bank Sta=4995.4,4999.4
Exp/Cntr=0.3,0.1

Chan Stop Cuts=-1