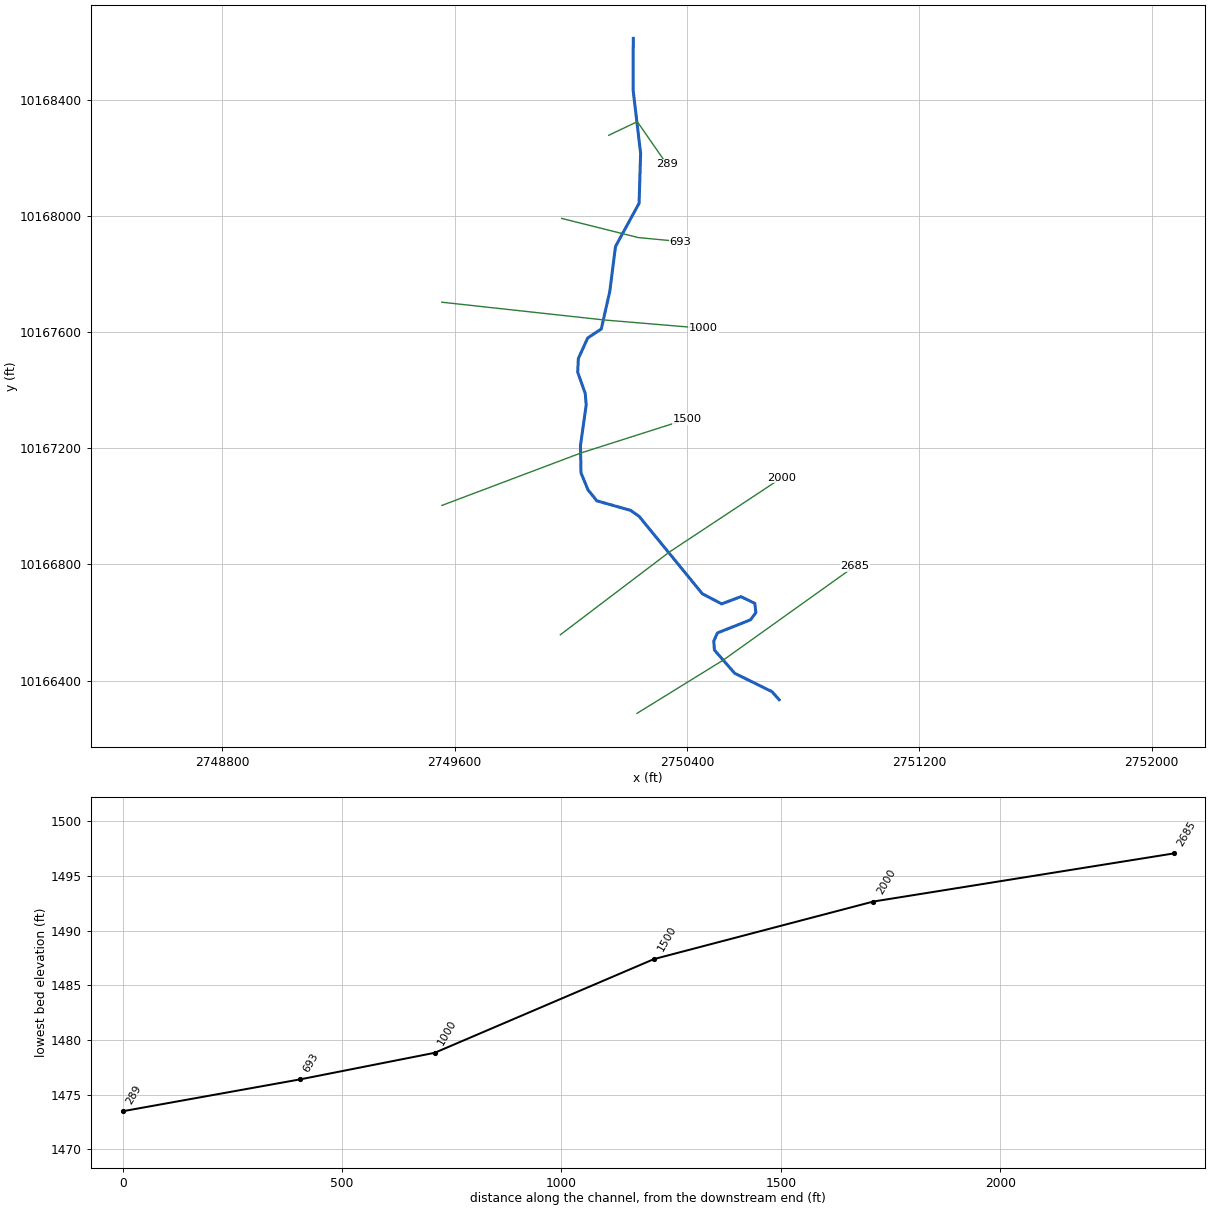
--- HICKORY27.prj (project) ---

Proj Title=HICKORY27 Base Level Engineering
Current Plan=p01
Default Exp/Contr=0.3,0.1
English Units
Geom File=g01
Flow File=f01
Plan File=p01
BEGIN DESCRIPTION:
HICKORY27
END DESCRIPTION:

--- HICKORY27.p01 (plan) ---

Plan Title=Multiple Run
Short Identifier=Multiple
Geom File=g01
Flow File=f01
Subcritical Flow
K Sum by GR= 0
Std Step Tol= 0.01
Critical Tol= 0.01
Num of Std Step Trials= 20
Max Error Tol= 0.3
Flow Tol Ratio= 0.001
Split Flow NTrial= 30
Split Flow Tol= 0.02
Split Flow Ratio= 0.02
Log Output Level= 0
Friction Slope Method= 1
Unsteady Friction Slope Method= 2
Unsteady Bridges Friction Slope Method= 1
Parabolic Critical Depth
Global Vel Dist=  1 , 1 , 1
Global Log Level= 0
CheckData=True
Encroach Param= -1, 0, 0, 0
BEGIN DESCRIPTION:
Multiple Run
END DESCRIPTION:

--- HICKORY27.f01 (steady flow) ---

Flow Title=Multiple
Number of Profiles=7
Profile Names=10-year,25-year,50-year,1pct_min,100-year,1pct_plu,500-year
River Rch & RM= HICKORY27,Reach-1,2685
     463     755    1308     994    1808    3288    2582
River Rch & RM= HICKORY27,Reach-1,1500
     502     825    1409    1048    1952    3634    2788
Boundary for River Rch & Prof#=HICKORY27,Reach-1,1
Up Type=0
Dn Type=3
Dn Slope=0.005
Boundary for River Rch & Prof#=HICKORY27,Reach-1,2
Up Type=0
Dn Type=3
Dn Slope=0.005
Boundary for River Rch & Prof#=HICKORY27,Reach-1,3
Up Type=0
Dn Type=3
Dn Slope=0.005
Boundary for River Rch & Prof#=HICKORY27,Reach-1,4
Up Type=0
Dn Type=3
Dn Slope=0.005
Boundary for River Rch & Prof#=HICKORY27,Reach-1,5
Up Type=0
Dn Type=3
Dn Slope=0.005
Boundary for River Rch & Prof#=HICKORY27,Reach-1,6
Up Type=0
Dn Type=3
Dn Slope=0.005
Boundary for River Rch & Prof#=HICKORY27,Reach-1,7
Up Type=0
Dn Type=3
Dn Slope=0.005

--- HICKORY27.g01 (geometry) ---

Geom Title=Existing Conditions

River Reach=HICKORY27,Reach-1
Reach XY= 30
      2750717.50     10166334.00      2750692.25     10166362.00
      2750564.25     10166425.00      2750494.50     10166505.00
      2750492.25     10166536.00      2750504.75     10166564.00
      2750618.50     10166609.00      2750637.25     10166634.00
      2750633.50     10166666.00      2750585.75     10166689.00
      2750519.50     10166664.00      2750452.75     10166699.00
      2750235.50     10166965.00      2750206.25     10166986.00
      2750089.50     10167019.00      2750059.00     10167057.00
      2750035.00     10167115.00      2750033.00     10167209.00
      2750052.75     10167349.00      2750049.50     10167389.00
      2750023.50     10167462.00      2750025.75     10167509.00
      2750058.00     10167580.00      2750104.75     10167611.00
      2750134.00     10167740.00      2750153.75     10167895.00
      2750235.00     10168044.00      2750240.25     10168216.00
      2750214.25     10168435.00      2750215.00     10168612.00

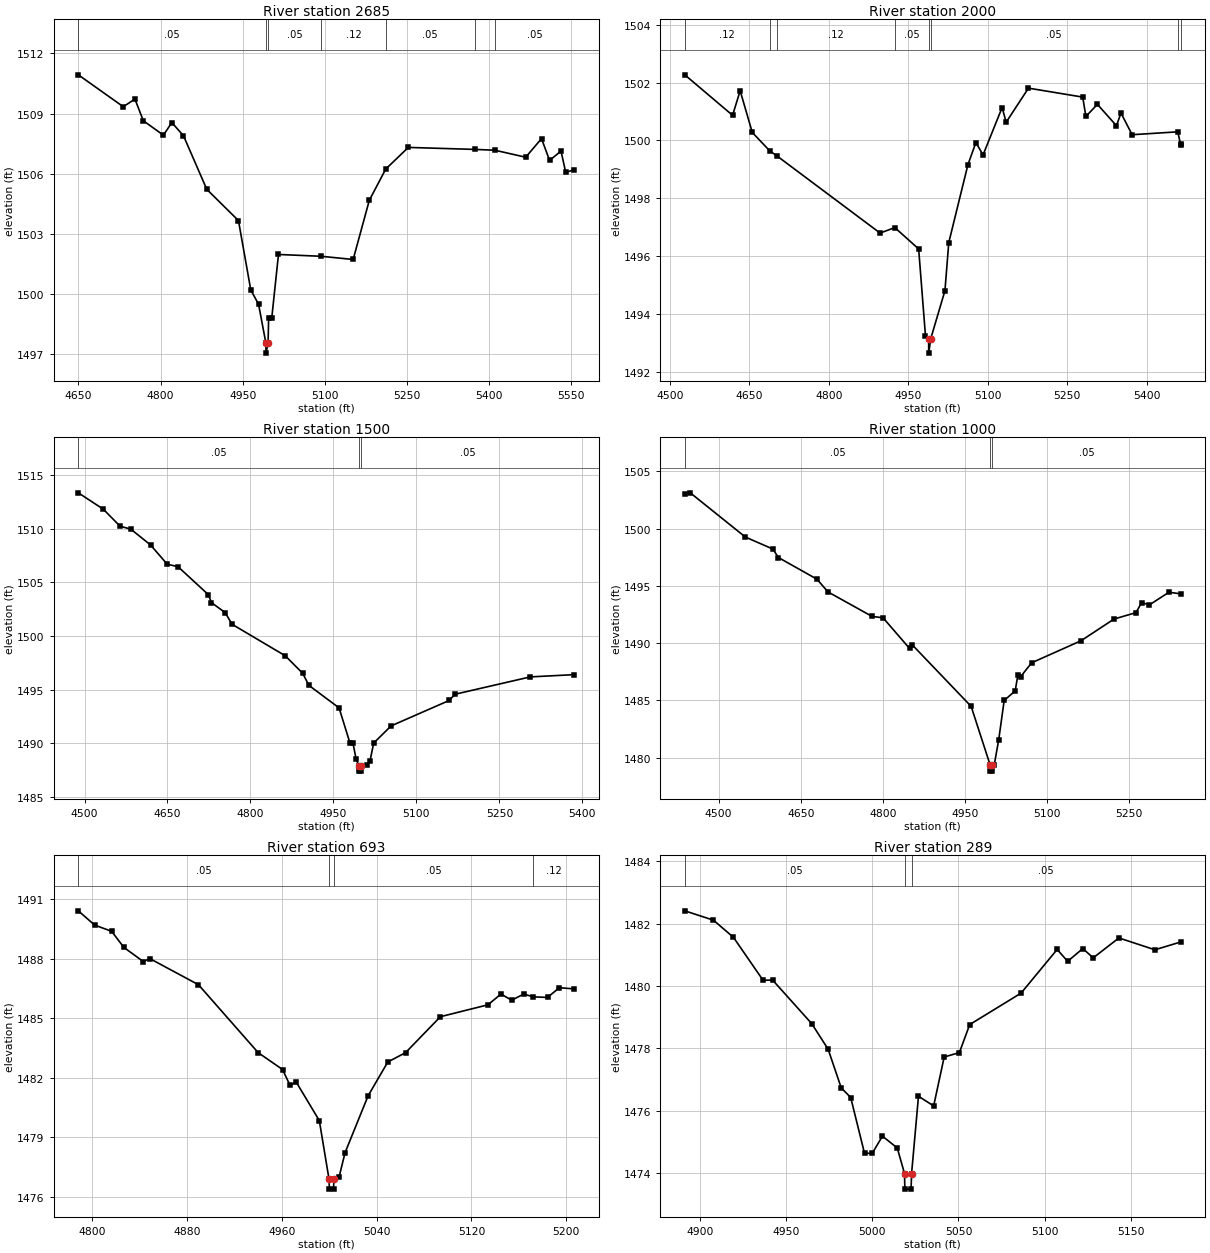
Type RM Length L Ch R = 1,2685,685,685,685
BEGIN DESCRIPTION:
HICKORY27 5.0
END DESCRIPTION:
XS GIS Cut Line= 3
      2750227.71     10166286.93      2750525.75     10166471.00
      2750977.67     10166793.86
#Sta/Elev= 30
  4649.7 1510.93  4731.8 1509.34  4753.1 1509.72  4768.4 1508.64  4805.1 1507.92
  4820.5 1508.55  4841.8 1507.89  4884.3 1505.22  4942.2 1503.66  4964.7 1500.20
  4978.9 1499.49  4992.3 1497.55  4992.5 1497.05  4996.3 1497.55  4997.3 1498.80
  5003.0 1498.80  5015.3 1501.97  5093.5 1501.88  5151.7 1501.72  5181.2 1504.67
  5211.2 1506.23  5252.5 1507.31  5374.0 1507.21  5410.7 1507.17  5466.9 1506.82
  5495.8 1507.75  5510.5 1506.66  5531.4 1507.13  5540.0 1506.06  5555.4 1506.20
#Mann=7,-1,0
  4649.7    0.05       0  4992.3    0.05       0  4996.3    0.05       0
  5093.5    0.12       0  5211.2    0.05       0  5374.0    0.12       0
  5410.7    0.05       0
Bank Sta=4992.3,4996.3
Exp/Cntr=0.3,0.1

Type RM Length L Ch R = 1,2000,500,500,500
BEGIN DESCRIPTION:
HICKORY27 4.0
END DESCRIPTION:
XS GIS Cut Line= 3
      2749963.80     10166557.75      2750339.52     10166842.78
      2750726.74     10167098.79
#Sta/Elev= 30
  4528.4 1502.27  4618.6 1500.87  4632.9 1501.72  4655.7 1500.28  4688.8 1499.64
  4702.1 1499.47  4897.0 1496.80  4924.8 1496.99  4969.8 1496.25  4982.6 1493.25
  4988.6 1493.15  4988.8 1492.65  4992.6 1493.15  5019.4 1494.81  5026.6 1496.47
  5062.7 1499.16  5077.8 1499.93  5091.3 1499.50  5127.3 1501.14  5134.9 1500.63
  5177.0 1501.81  5279.4 1501.50  5285.4 1500.83  5307.1 1501.25  5343.1 1500.51
  5351.6 1500.95  5372.7 1500.20  5458.9 1500.30  5464.0 1499.87  5464.2 1499.85
#Mann=8,-1,0
  4528.4    0.12       0  4688.8    0.05       0  4702.1    0.12       0
  4924.8    0.05       0  4988.6    0.05       0  4992.6    0.05       0
  5458.9    0.12       0  5464.0    0.05       0
Bank Sta=4988.6,4992.6
Exp/Cntr=0.3,0.1

Type RM Length L Ch R = 1,1500,500,500,500
BEGIN DESCRIPTION:
HICKORY27 3.0
END DESCRIPTION:
XS GIS Cut Line= 3
      2749555.72     10167003.13      2750034.00     10167183.62
      2750400.97     10167300.71
#Sta/Elev= 30
  4488.8 1513.35  4534.0 1511.82  4564.2 1510.24  4583.7 1509.96  4619.3 1508.49
  4649.5 1506.69  4669.0 1506.46  4723.9 1503.85  4729.4 1503.11  4754.2 1502.18
  4766.7 1501.09  4862.9 1498.15  4894.5 1496.51  4905.6 1495.39  4960.2 1493.29
  4979.7 1490.04  4985.1 1490.06  4991.1 1488.48  4996.2 1487.89  4996.5 1487.39
  5000.0 1487.39  5000.2 1487.89  5010.9 1487.92  5016.2 1488.37  5022.8 1490.01
  5054.3 1491.61  5159.2 1493.98  5169.7 1494.56  5305.9 1496.18  5385.2 1496.39
#Mann=3,-1,0
  4488.8    0.05       0  4996.2    0.05       0  5000.2    0.05       0
Bank Sta=4996.2,5000.2
Exp/Cntr=0.3,0.1

Type RM Length L Ch R = 1,1000,307,307,307
BEGIN DESCRIPTION:
HICKORY27 2.0
END DESCRIPTION:
XS GIS Cut Line= 3
      2749555.70     10167703.11      2750114.17     10167642.01
      2750456.87     10167613.32
#Sta/Elev= 30
  4438.2 1503.00  4448.2 1503.12  4548.8 1499.26  4599.1 1498.21  4609.2 1497.47
  4679.6 1495.58  4699.7 1494.47  4780.2 1492.33  4800.3 1492.21  4848.8 1489.53
  4853.8 1489.84  4961.3 1484.47  4996.2 1479.32  4996.5 1478.82  5000.0 1478.82
  5000.2 1479.32  5003.3 1479.32  5011.6 1481.56  5021.6 1484.99  5041.7 1485.83
  5046.7 1487.24  5051.7 1487.07  5071.8 1488.28  5161.8 1490.20  5222.3 1492.10
  5262.4 1492.66  5272.5 1493.53  5287.0 1493.34  5322.6 1494.44  5343.9 1494.30
#Mann=3,-1,0
  4438.2    0.05       0  4996.2    0.05       0  5000.2    0.05       0
Bank Sta=4996.2,5000.2
Exp/Cntr=0.3,0.1

Type RM Length L Ch R = 1,693,404,404,404
BEGIN DESCRIPTION:
Mapping XS 8c93f97e
END DESCRIPTION:
XS GIS Cut Line= 3
      2749968.39     10167991.73      2750232.31     10167925.75
      2750378.11     10167911.87
#Sta/Elev= 30
  4788.2 1490.40  4802.0 1489.68  4816.3 1489.37  4826.6 1488.56  4843.2 1487.84
  4848.4 1488.00  4889.6 1486.68  4940.0 1483.26  4960.6 1482.41  4966.9 1481.61
  4972.1 1481.78  4991.6 1479.84  4999.8 1476.89  5000.1 1476.39  5003.6 1476.39
  5003.9 1476.89  5008.2 1476.98  5013.3 1478.22  5032.8 1481.09  5049.4 1482.79
  5064.4 1483.26  5093.8 1485.07  5134.0 1485.67  5144.9 1486.21  5154.0 1485.90
  5164.1 1486.21  5172.3 1486.07  5184.2 1486.04  5194.2 1486.53  5206.7 1486.47
#Mann=4,-1,0
  4788.2    0.05       0  4999.8    0.05       0  5003.9    0.05       0
  5172.3    0.12       0
Bank Sta=4999.8,5003.9
Exp/Cntr=0.3,0.1

Type RM Length L Ch R = 1,289,0,0,0
BEGIN DESCRIPTION:
HICKORY27 1.0
END DESCRIPTION:
XS GIS Cut Line= 3
      2750130.68     10168278.11      2750228.75     10168325.00
      2750330.69     10168178.11
#Sta/Elev= 30
  4891.3 1482.41  4907.9 1482.11  4919.5 1481.56  4936.7 1480.18  4942.2 1480.19
  4964.9 1478.79  4974.4 1477.97  4982.0 1476.73  4987.5 1476.42  4995.5 1474.63
  5000.0 1474.63  5005.9 1475.18  5014.5 1474.80  5018.7 1473.98  5018.9 1473.48
  5022.5 1473.48  5022.8 1473.98  5026.8 1476.46  5035.6 1476.15  5041.7 1477.72
  5050.5 1477.86  5056.5 1478.76  5086.3 1479.77  5107.2 1481.17  5113.3 1480.79
  5122.1 1481.20  5128.1 1480.90  5143.0 1481.54  5163.9 1481.16  5178.8 1481.41
#Mann=3,-1,0
  4891.3    0.05       0  5018.7    0.05       0  5022.8    0.05       0
Bank Sta=5018.7,5022.8
Exp/Cntr=0.3,0.1

Chan Stop Cuts=-1