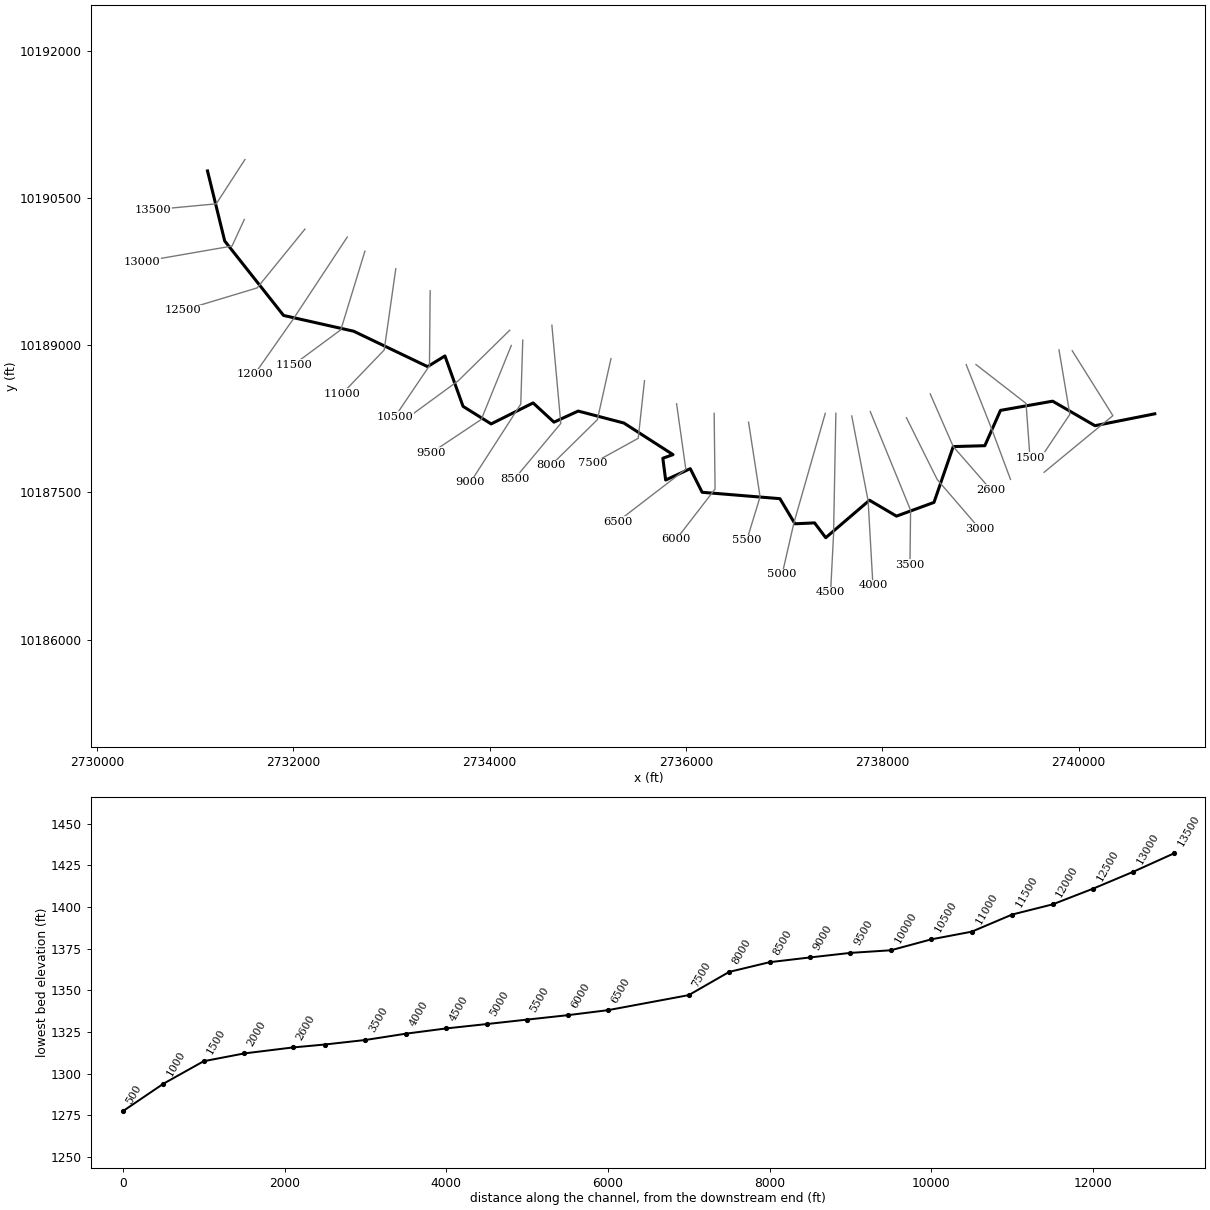
--- HICKORY28.prj (project) ---

Proj Title=HICKORY28 Base Level Engineering
Current Plan=p01
Default Exp/Contr=0.3,0.1
English Units
Geom File=g01
Flow File=f01
Plan File=p01
BEGIN DESCRIPTION:
HICKORY28
END DESCRIPTION:

--- HICKORY28.p01 (plan) ---

Plan Title=Multiple Run
Short Identifier=Multiple
Geom File=g01
Flow File=f01
Subcritical Flow
K Sum by GR= 0
Std Step Tol= 0.01
Critical Tol= 0.01
Num of Std Step Trials= 20
Max Error Tol= 0.3
Flow Tol Ratio= 0.001
Split Flow NTrial= 30
Split Flow Tol= 0.02
Split Flow Ratio= 0.02
Log Output Level= 0
Friction Slope Method= 1
Unsteady Friction Slope Method= 2
Unsteady Bridges Friction Slope Method= 1
Parabolic Critical Depth
Global Vel Dist=  1 , 1 , 1
Global Log Level= 0
CheckData=True
Encroach Param= -1, 0, 0, 0
BEGIN DESCRIPTION:
Multiple Run
END DESCRIPTION:

--- HICKORY28.f01 (steady flow) ---

Flow Title=Multiple
Number of Profiles=7
Profile Names=10-year,25-year,50-year,1pct_min,100-year,1pct_plu,500-year
River Rch & RM= HICKORY28,Reach-1,13500
     538     892    1340     946    1839    3572    2601
Boundary for River Rch & Prof#=HICKORY28,Reach-1,1
Up Type=0
Dn Type=3
Dn Slope=0.005
Boundary for River Rch & Prof#=HICKORY28,Reach-1,2
Up Type=0
Dn Type=3
Dn Slope=0.005
Boundary for River Rch & Prof#=HICKORY28,Reach-1,3
Up Type=0
Dn Type=3
Dn Slope=0.005
Boundary for River Rch & Prof#=HICKORY28,Reach-1,4
Up Type=0
Dn Type=3
Dn Slope=0.005
Boundary for River Rch & Prof#=HICKORY28,Reach-1,5
Up Type=0
Dn Type=3
Dn Slope=0.005
Boundary for River Rch & Prof#=HICKORY28,Reach-1,6
Up Type=0
Dn Type=3
Dn Slope=0.005
Boundary for River Rch & Prof#=HICKORY28,Reach-1,7
Up Type=0
Dn Type=3
Dn Slope=0.005

--- HICKORY28.g01 (geometry) ---

Geom Title=Existing Conditions

River Reach=HICKORY28,Reach-1
Reach XY= 30
      2731127.00     10190777.00      2731302.25     10190063.00
      2731901.75     10189304.00      2732616.25     10189143.00
      2733369.00     10188782.00      2733545.75     10188891.00
      2733730.25     10188377.00      2734016.50     10188198.00
      2734444.00     10188412.00      2734656.50     10188216.00
      2734903.25     10188329.00      2735369.00     10188207.00
      2735869.25     10187885.00      2735765.50     10187848.00
      2735794.25     10187626.00      2736045.00     10187742.00
      2736166.00     10187501.00      2736958.25     10187436.00
      2737111.50     10187180.00      2737311.50     10187189.00
      2737425.00     10187038.00      2737870.75     10187420.00
      2738145.75     10187258.00      2738527.75     10187398.00
      2738724.00     10187967.00      2739045.75     10187976.00
      2739205.25     10188336.00      2739736.50     10188430.00
      2740167.75     10188180.00      2740777.00     10188301.00

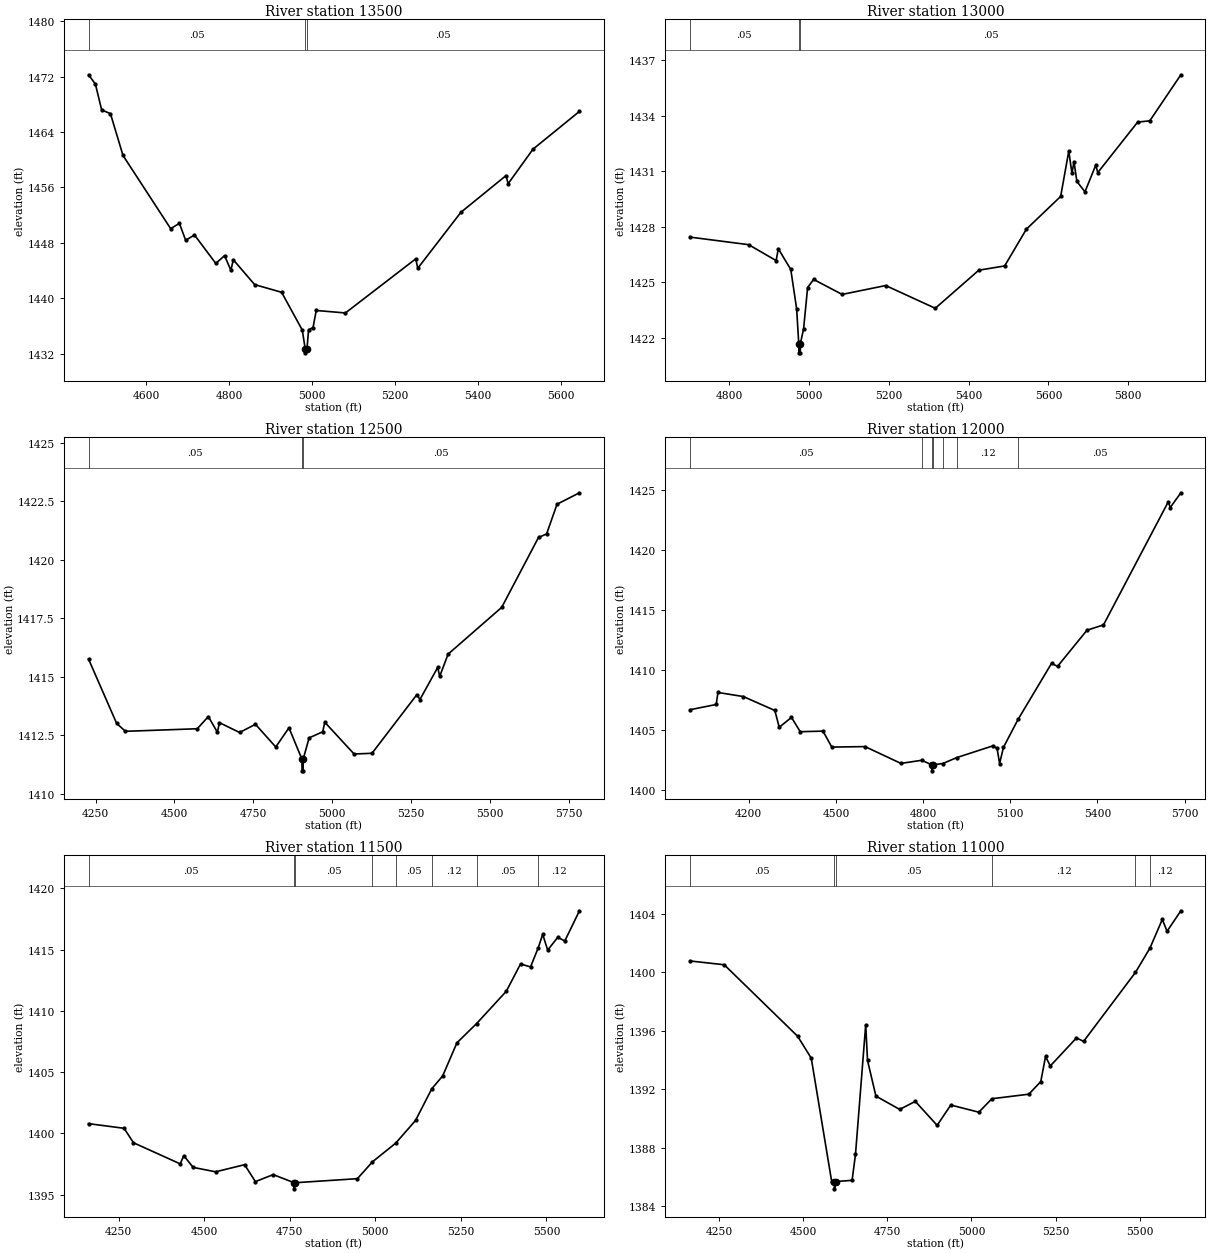
Type RM Length L Ch R = 1,13500,500,500,500
BEGIN DESCRIPTION:
HICKORY28 26.0
END DESCRIPTION:
XS GIS Cut Line= 3
      2731508.53     10190893.74      2731215.95     10190441.78
      2730574.16     10190381.63
#Sta/Elev= 30
  4461.6 1472.25  4478.1 1470.92  4493.3 1467.17  4514.4 1466.65  4544.7 1460.61
  4659.5 1450.06  4680.6 1450.82  4695.7 1448.38  4716.9 1449.15  4768.3 1445.04
  4789.4 1446.17  4804.6 1444.05  4810.5 1445.57  4861.9 1441.99  4926.9 1440.88
  4976.7 1435.43  4983.9 1432.65  4984.2 1432.15  4987.9 1432.65  4991.9 1435.49
  5002.6 1435.79  5010.3 1438.26  5080.6 1437.90  5250.0 1445.70  5255.0 1444.35
  5358.8 1452.41  5467.6 1457.71  5472.7 1456.54  5532.6 1461.52  5644.6 1466.97
#Mann=3,-1,0
  4461.6    0.05       0  4983.9    0.05       0  4987.9    0.05       0
Bank Sta=4983.9,4987.9
Exp/Cntr=0.3,0.1

Type RM Length L Ch R = 1,13000,500,500,500
BEGIN DESCRIPTION:
HICKORY28 25.0
END DESCRIPTION:
XS GIS Cut Line= 3
      2731501.94     10190282.58      2731376.89     10190011.53
      2730458.98     10189851.83
#Sta/Elev= 30
  4701.5 1427.44  4848.7 1427.03  4917.5 1426.17  4923.0 1426.81  4954.2 1425.69
  4968.9 1423.56  4974.2 1421.68  4974.5 1421.18  4978.0 1421.18  4978.2 1421.68
  4986.3 1422.47  4996.4 1424.71  5011.4 1425.15  5082.9 1424.34  5192.0 1424.82
  5316.3 1423.59  5425.4 1425.65  5490.1 1425.88  5544.6 1427.87  5630.5 1429.64
  5650.8 1432.09  5658.8 1430.89  5663.9 1431.52  5671.1 1430.45  5691.4 1429.89
  5718.4 1431.33  5723.5 1430.93  5823.4 1433.66  5853.8 1433.73  5931.7 1436.22
#Mann=3,-1,0
  4701.5    0.05       0  4974.2    0.05       0  4978.2    0.05       0
Bank Sta=4974.2,4978.2
Exp/Cntr=0.3,0.1

Type RM Length L Ch R = 1,12500,500,500,500
BEGIN DESCRIPTION:
HICKORY28 24.0
END DESCRIPTION:
XS GIS Cut Line= 3
      2732119.51     10190184.00      2731632.50     10189584.48
      2730881.33     10189357.91
#Sta/Elev= 30
  4227.6 1415.76  4316.7 1413.01  4344.7 1412.67  4572.4 1412.78  4607.6 1413.30
  4636.3 1412.63  4642.8 1413.04  4706.7 1412.62  4757.0 1412.97  4821.4 1412.00
  4863.3 1412.82  4904.4 1411.48  4904.7 1410.98  4908.2 1410.98  4908.4 1411.48
  4927.2 1412.39  4970.4 1412.65  4976.8 1413.06  5069.8 1411.70  5126.6 1411.73
  5269.0 1414.24  5278.7 1414.03  5334.9 1415.40  5341.4 1415.02  5367.9 1415.97
  5538.0 1417.97  5654.7 1420.96  5680.4 1421.11  5713.4 1422.38  5784.6 1422.87
#Mann=3,-1,0
  4227.6    0.05       0  4904.4    0.03       0  4908.4    0.05       0
Bank Sta=4904.4,4908.4
Exp/Cntr=0.3,0.1

Type RM Length L Ch R = 1,12000,500,500,500
BEGIN DESCRIPTION:
HICKORY28 23.0
END DESCRIPTION:
XS GIS Cut Line= 3
      2732550.75     10190103.12      2731999.74     10189265.87
      2731605.69     10188703.11
#Sta/Elev= 30
  3997.7 1406.65  4088.1 1407.09  4094.1 1408.09  4181.5 1407.75  4289.9 1406.59
  4305.0 1405.19  4347.1 1406.01  4377.3 1404.82  4455.6 1404.87  4485.8 1403.54
  4600.2 1403.58  4723.7 1402.18  4795.2 1402.44  4830.1 1402.06  4830.4 1401.56
  4834.1 1402.06  4867.9 1402.17  4916.5 1402.67  5040.0 1403.64  5054.5 1403.45
  5063.2 1402.17  5076.6 1403.52  5126.9 1405.85  5241.9 1410.51  5262.8 1410.27
  5364.0 1413.28  5420.7 1413.72  5643.8 1423.98  5650.4 1423.50  5687.0 1424.73
#Mann=7,-1,0
  3997.7    0.05       0  4795.2    0.12       0  4830.1    0.07       0
  4834.1    0.12       0  4867.9    0.05       0  4916.5    0.12       0
  5126.9    0.05       0
Bank Sta=4830.1,4834.1
Exp/Cntr=0.3,0.1

Type RM Length L Ch R = 1,11500,500,500,500
BEGIN DESCRIPTION:
HICKORY28 22.0
END DESCRIPTION:
XS GIS Cut Line= 3
      2732730.45     10189959.40      2732485.42     10189157.81
      2732005.71     10188803.13
#Sta/Elev= 30
  4161.8 1400.79  4265.7 1400.41  4293.2 1399.23  4429.6 1397.51  4440.3 1398.17
  4467.6 1397.22  4533.2 1396.86  4618.0 1397.44  4649.4 1396.06  4701.7 1396.63
  4762.4 1395.97  4762.7 1395.47  4766.4 1395.97  4947.6 1396.30  4991.5 1397.67
  5059.6 1399.20  5117.5 1401.05  5164.9 1403.63  5196.9 1404.69  5238.6 1407.39
  5296.1 1408.96  5382.7 1411.59  5424.4 1413.82  5453.6 1413.58  5476.3 1415.15
  5489.1 1416.24  5503.7 1414.95  5533.0 1415.99  5553.8 1415.70  5596.6 1418.16
#Mann=8,-1,0
  4161.8    0.05       0  4762.4    0.07       0  4766.4    0.05       0
  4991.5    0.12       0  5059.6    0.05       0  5164.9    0.12       0
  5296.1    0.05       0  5476.3    0.12       0
Bank Sta=4762.4,4766.4
Exp/Cntr=0.3,0.1

Type RM Length L Ch R = 1,11000,500,500,500
BEGIN DESCRIPTION:
HICKORY28 21.0
END DESCRIPTION:
XS GIS Cut Line= 3
      2733044.90     10189779.70      2732927.33     10188952.21
      2732496.81     10188503.83
#Sta/Elev= 30
  4164.2 1400.76  4266.0 1400.50  4484.0 1395.61  4524.4 1394.11  4585.0 1385.68
  4593.1 1385.68  4593.3 1385.18  4597.1 1385.68  4645.6 1385.76  4655.7 1387.54
  4686.0 1396.39  4691.4 1393.96  4716.3 1391.52  4787.0 1390.61  4833.2 1391.16
  4898.1 1389.52  4938.5 1390.91  5021.8 1390.42  5060.6 1391.34  5170.2 1391.65
  5205.7 1392.51  5219.9 1394.23  5234.0 1393.58  5311.7 1395.50  5332.8 1395.26
  5486.9 1399.98  5529.8 1401.64  5566.5 1403.60  5580.6 1402.79  5621.6 1404.19
#Mann=6,-1,0
  4164.2    0.05       0  4593.1    0.05       0  4597.1    0.05       0
  5060.6    0.12       0  5486.9    0.05       0  5529.8    0.12       0
Bank Sta=4593.1,4597.1
Exp/Cntr=0.3,0.1

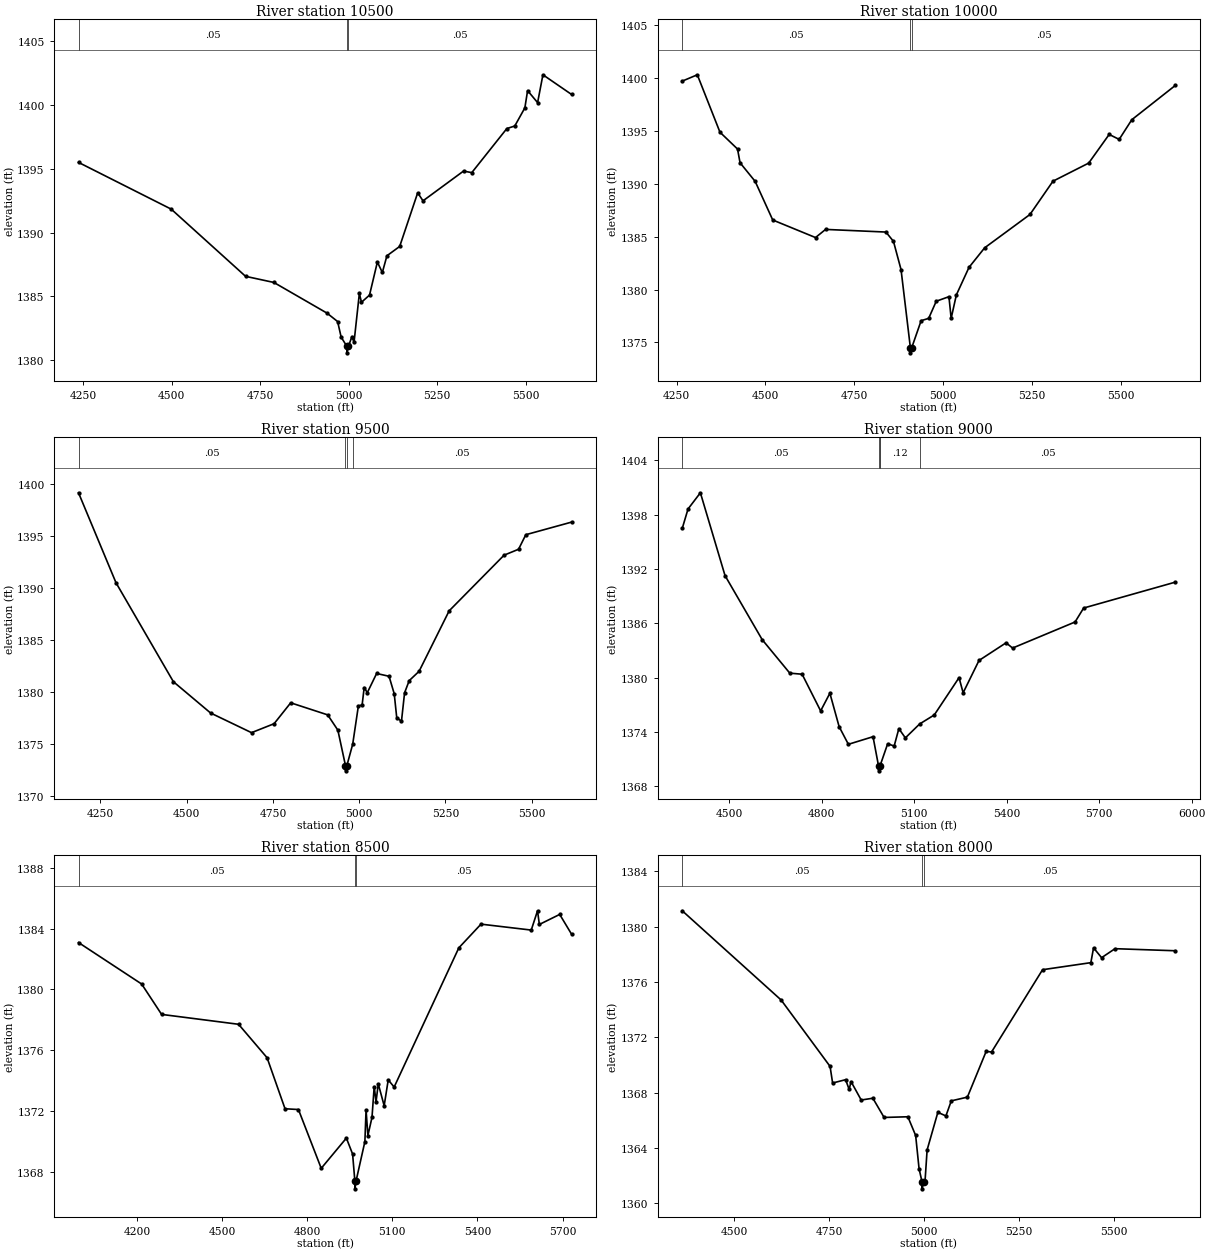
Type RM Length L Ch R = 1,10500,500,500,500
BEGIN DESCRIPTION:
HICKORY28 20.0
END DESCRIPTION:
XS GIS Cut Line= 3
      2733395.30     10189555.03      2733388.23     10188791.66
      2733035.90     10188270.24
#Sta/Elev= 30
  4236.6 1395.49  4498.5 1391.83  4708.5 1386.57  4788.5 1386.09  4938.5 1383.69
  4968.5 1383.03  4978.5 1381.81  4994.8 1381.08  4995.0 1380.58  4998.8 1381.08
  5008.9 1381.85  5014.9 1381.41  5029.9 1385.23  5035.9 1384.54  5058.6 1385.10
  5080.8 1387.69  5094.8 1386.87  5107.8 1388.18  5143.8 1388.91  5194.7 1393.11
  5209.7 1392.48  5324.1 1394.81  5347.5 1394.69  5446.5 1398.14  5468.9 1398.34
  5497.4 1399.76  5505.1 1401.11  5533.4 1400.17  5548.4 1402.35  5629.3 1400.81
#Mann=3,-1,0
  4236.6    0.05       0  4994.8    0.05       0  4998.8    0.05       0
Bank Sta=4994.8,4998.8
Exp/Cntr=0.3,0.1

Type RM Length L Ch R = 1,10000,500,500,500
BEGIN DESCRIPTION:
HICKORY28 19.0
END DESCRIPTION:
XS GIS Cut Line= 3
      2734205.68     10189153.11      2733682.07     10188638.73
      2733155.70     10188253.12
#Sta/Elev= 30
  4266.0 1399.71  4308.4 1400.31  4372.1 1394.88  4421.5 1393.29  4428.6 1391.99
  4471.1 1390.23  4520.5 1386.58  4640.8 1384.92  4669.1 1385.69  4838.8 1385.44
  4860.0 1384.56  4881.3 1381.89  4907.5 1374.52  4907.8 1374.02  4911.5 1374.52
  4937.8 1377.06  4959.0 1377.28  4980.3 1378.90  5016.0 1379.33  5022.2 1377.28
  5036.9 1379.50  5072.4 1382.10  5116.4 1383.95  5243.8 1387.10  5308.6 1390.25
  5409.0 1391.96  5466.6 1394.67  5494.7 1394.20  5530.2 1396.06  5652.5 1399.30
#Mann=3,-1,0
  4266.0    0.05       0  4907.5    0.05       0  4911.5    0.05       0
Bank Sta=4907.5,4911.5
Exp/Cntr=0.3,0.1

Type RM Length L Ch R = 1,9500,500,500,500
BEGIN DESCRIPTION:
HICKORY28 18.0
END DESCRIPTION:
XS GIS Cut Line= 3
      2734221.87     10188997.97      2733916.22     10188243.86
      2733404.24     10187901.86
#Sta/Elev= 30
  4186.3 1399.18  4295.0 1390.53  4461.3 1381.02  4569.2 1378.01  4687.9 1376.12
  4753.3 1376.98  4801.5 1378.99  4908.7 1377.83  4938.2 1376.36  4960.3 1372.95
  4960.5 1372.45  4964.3 1372.95  4981.2 1375.01  4997.7 1378.70  5008.5 1378.77
  5014.5 1380.46  5023.5 1379.96  5050.6 1381.81  5086.6 1381.54  5101.6 1379.86
  5108.9 1377.55  5122.6 1377.22  5131.6 1379.95  5145.0 1381.12  5173.7 1382.02
  5260.8 1387.83  5420.0 1393.18  5462.0 1393.75  5483.1 1395.15  5615.7 1396.36
#Mann=4,-1,0
  4186.3    0.05       0  4960.3    0.05       0  4964.3    0.05       0
  4981.2    0.05       0
Bank Sta=4960.3,4964.3
Exp/Cntr=0.3,0.1

Type RM Length L Ch R = 1,9000,500,500,500
BEGIN DESCRIPTION:
HICKORY28 17.0
END DESCRIPTION:
XS GIS Cut Line= 3
      2734338.68     10189051.95      2734318.20     10188399.27
      2733805.66     10187603.08
#Sta/Elev= 30
  4347.0 1396.49  4365.8 1398.64  4405.9 1400.43  4485.9 1391.28  4606.4 1384.21
  4696.0 1380.51  4736.0 1380.39  4796.1 1376.34  4826.1 1378.29  4856.1 1374.60
  4886.1 1372.65  4966.1 1373.49  4984.2 1370.22  4984.4 1369.72  4988.2 1370.22
  4988.4 1370.23  5013.6 1372.71  5034.7 1372.46  5049.9 1374.38  5071.0 1373.36
  5117.5 1374.90  5164.8 1375.89  5245.2 1380.01  5258.5 1378.34  5310.0 1381.91
  5397.8 1383.86  5419.0 1383.28  5621.7 1386.16  5649.5 1387.70  5946.9 1390.56
#Mann=5,-1,0
  4347.0    0.05       0  4984.2    0.07       0  4988.2    0.05       0
  4988.4    0.12       0  5117.5    0.05       0
Bank Sta=4984.2,4988.2
Exp/Cntr=0.3,0.1

Type RM Length L Ch R = 1,8500,500,500,500
BEGIN DESCRIPTION:
HICKORY28 16.0
END DESCRIPTION:
XS GIS Cut Line= 3
      2734635.17     10189204.62      2734725.97     10188203.33
      2734257.84     10187641.36
#Sta/Elev= 30
  3994.6 1383.08  4217.0 1380.35  4287.3 1378.35  4558.4 1377.70  4658.8 1375.50
  4722.1 1372.14  4769.3 1372.09  4849.6 1368.22  4938.2 1370.21  4960.1 1369.16
  4968.1 1367.37  4968.3 1366.87  4972.1 1367.37  5003.4 1369.98  5007.5 1372.06
  5014.0 1370.38  5028.4 1371.57  5036.2 1373.60  5042.7 1372.60  5050.5 1373.78
  5071.3 1372.34  5085.6 1374.04  5106.5 1373.57  5334.3 1382.73  5412.4 1384.29
  5589.4 1383.90  5611.5 1385.17  5618.0 1384.27  5689.6 1384.93  5731.4 1383.63
#Mann=3,-1,0
  3994.6    0.05       0  4968.1    0.03       0  4972.1    0.05       0
Bank Sta=4968.1,4972.1
Exp/Cntr=0.3,0.1

Type RM Length L Ch R = 1,8000,500,500,500
BEGIN DESCRIPTION:
HICKORY28 15.0
END DESCRIPTION:
XS GIS Cut Line= 3
      2735237.13     10188863.22      2735098.62     10188241.35
      2734627.23     10187777.13
#Sta/Elev= 30
  4362.9 1381.15  4623.4 1374.70  4752.3 1369.90  4759.0 1368.70  4793.3 1368.94
  4802.5 1368.24  4807.6 1368.80  4834.3 1367.47  4865.0 1367.60  4894.6 1366.21
  4957.2 1366.26  4977.7 1364.91  4986.7 1362.51  4994.5 1361.55  4994.8 1361.05
  4998.5 1361.55  5002.3 1361.55  5007.9 1363.86  5036.2 1366.58  5057.4 1366.32
  5071.6 1367.41  5114.0 1367.68  5163.5 1370.99  5177.6 1370.94  5312.0 1376.89
  5439.2 1377.40  5446.3 1378.47  5467.5 1377.76  5502.9 1378.41  5661.6 1378.26
#Mann=3,-1,0
  4362.9    0.05       0  4994.5    0.05       0  4998.5    0.05       0
Bank Sta=4994.5,4998.5
Exp/Cntr=0.3,0.1

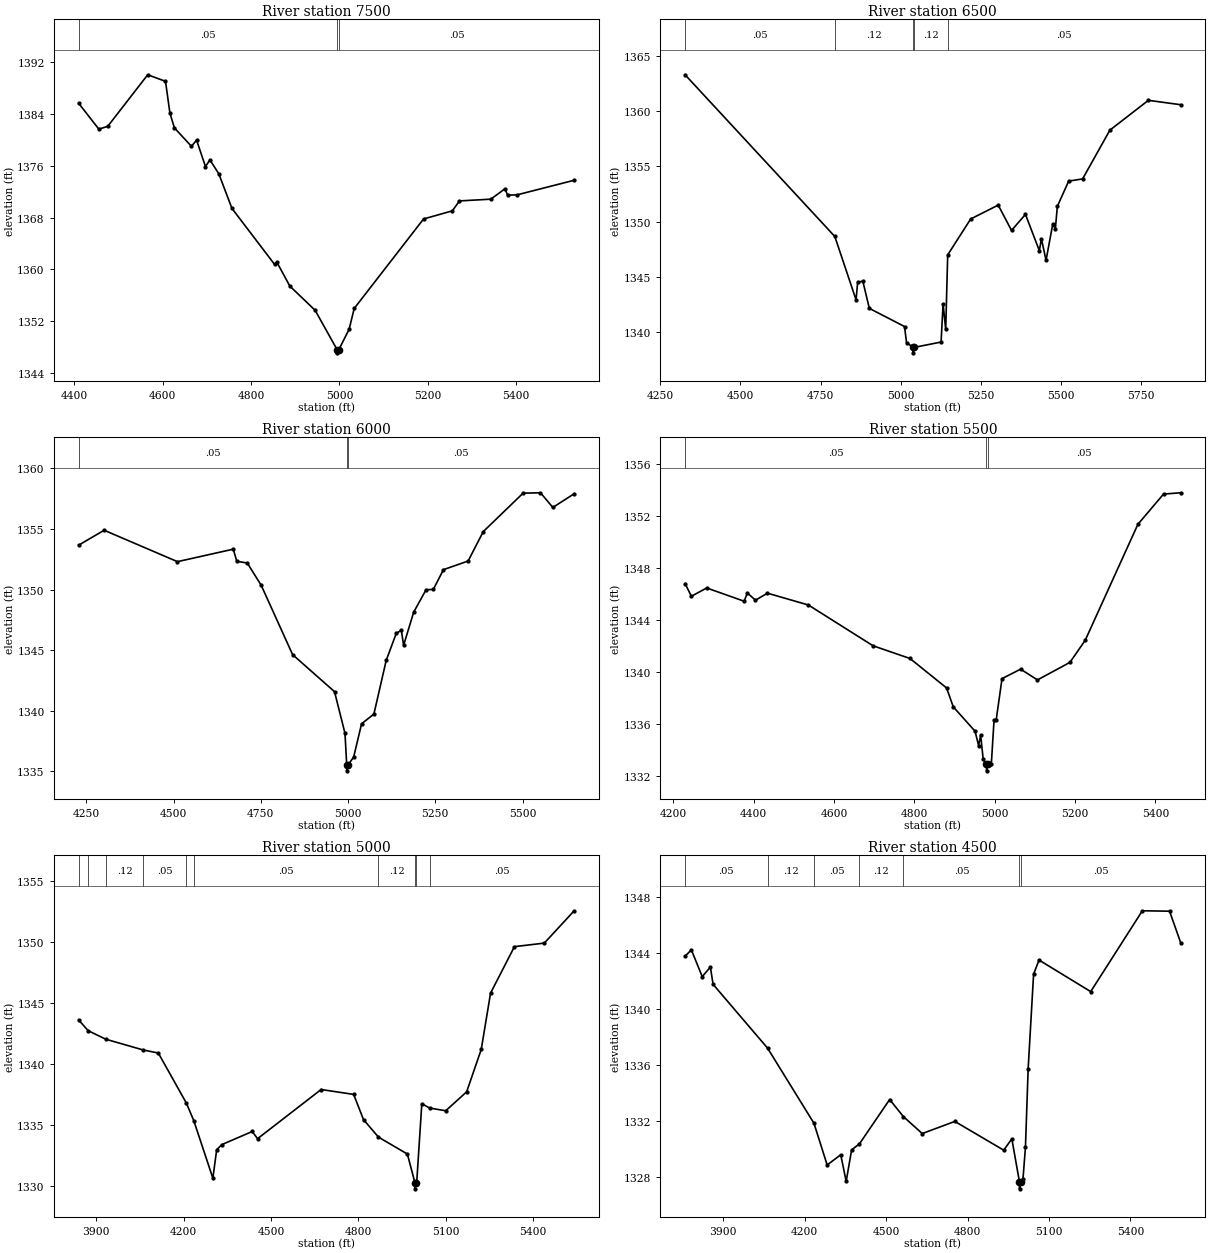
Type RM Length L Ch R = 1,7500,1000,1000,1000
BEGIN DESCRIPTION:
HICKORY28 14.0
END DESCRIPTION:
XS GIS Cut Line= 3
      2735578.55     10188638.63      2735514.96     10188051.57
      2735049.56     10187794.67
#Sta/Elev= 30
  4409.5 1385.64  4455.3 1381.64  4475.4 1382.07  4565.9 1390.03  4606.2 1389.02
  4616.2 1384.12  4626.3 1381.84  4664.9 1378.99  4676.6 1379.94  4696.7 1375.87
  4706.8 1376.89  4726.9 1374.75  4756.6 1369.41  4853.3 1360.75  4858.3 1361.11
  4887.8 1357.41  4945.0 1353.68  4994.7 1347.61  4995.0 1347.11  4998.7 1347.61
  5022.0 1350.74  5033.5 1353.96  5190.5 1367.77  5255.8 1369.03  5271.9 1370.56
  5342.9 1370.83  5375.0 1372.44  5380.7 1371.45  5402.5 1371.50  5531.6 1373.75
#Mann=3,-1,0
  4409.5    0.05       0  4994.7    0.05       0  4998.7    0.05       0
Bank Sta=4994.7,4998.7
Exp/Cntr=0.3,0.1

Type RM Length L Ch R = 1,6500,500,500,500
BEGIN DESCRIPTION:
HICKORY28 13.0
END DESCRIPTION:
XS GIS Cut Line= 3
      2735905.69     10188403.10      2735999.48     10187736.56
      2735305.66     10187203.09
#Sta/Elev= 30
  4326.9 1363.33  4794.7 1348.64  4861.1 1342.88  4866.1 1344.50  4882.3 1344.57
  4902.5 1342.11  5012.5 1340.46  5018.8 1338.99  5039.5 1338.57  5039.7 1338.07
  5043.5 1338.57  5126.7 1339.05  5133.0 1342.51  5141.2 1340.20  5147.4 1346.97
  5219.2 1350.23  5305.2 1351.49  5346.8 1349.19  5390.4 1350.65  5433.7 1347.35
  5440.2 1348.42  5454.7 1346.48  5475.5 1349.75  5483.7 1349.32  5490.0 1351.38
  5525.4 1353.67  5568.9 1353.87  5654.1 1358.30  5774.5 1361.01  5875.2 1360.61
#Mann=5,-1,0
  4326.9    0.05       0  4794.7    0.12       0  5039.5    0.07       0
  5043.5    0.12       0  5147.4    0.05       0
Bank Sta=5039.5,5043.5
Exp/Cntr=0.3,0.1

Type RM Length L Ch R = 1,6000,500,500,500
BEGIN DESCRIPTION:
HICKORY28 12.0
END DESCRIPTION:
XS GIS Cut Line= 3
      2736288.33     10188306.18      2736297.72     10187534.44
      2735902.02     10187021.42
#Sta/Elev= 30
  4228.2 1353.66  4301.3 1354.89  4511.3 1352.30  4671.3 1353.33  4681.3 1352.33
  4711.3 1352.19  4751.3 1350.35  4841.3 1344.63  4961.3 1341.58  4991.3 1338.14
  4996.2 1335.55  4996.4 1335.05  5000.2 1335.55  5016.1 1336.18  5038.8 1338.93
  5074.1 1339.73  5109.4 1344.16  5138.4 1346.40  5152.9 1346.63  5159.2 1345.40
  5188.2 1348.14  5223.5 1349.98  5244.3 1350.01  5273.4 1351.64  5344.0 1352.35
  5387.5 1354.78  5501.6 1357.95  5551.4 1357.98  5586.8 1356.77  5647.9 1357.90
#Mann=3,-1,0
  4228.2    0.05       0  4996.2    0.05       0  5000.2    0.05       0
Bank Sta=4996.2,5000.2
Exp/Cntr=0.3,0.1

Type RM Length L Ch R = 1,5500,500,500,500
BEGIN DESCRIPTION:
HICKORY28 11.0
END DESCRIPTION:
XS GIS Cut Line= 3
      2736638.74     10188216.30      2736756.22     10187454.81
      2736620.76     10187012.38
#Sta/Elev= 30
  4229.5 1346.83  4245.1 1345.85  4283.3 1346.49  4376.4 1345.47  4384.5 1346.10
  4404.7 1345.55  4434.5 1346.09  4536.3 1345.18  4697.2 1342.04  4789.2 1341.06
  4880.3 1338.79  4896.8 1337.34  4951.1 1335.46  4959.9 1334.36  4965.0 1335.14
  4971.4 1333.30  4979.5 1332.91  4979.7 1332.41  4983.5 1332.91  4991.6 1332.95
  4998.3 1336.29  5003.5 1336.29  5018.2 1339.51  5064.5 1340.24  5106.4 1339.41
  5187.2 1340.76  5225.2 1342.46  5356.3 1351.39  5420.1 1353.72  5462.7 1353.82
#Mann=3,-1,0
  4229.5    0.05       0  4979.5    0.03       0  4983.5    0.05       0
Bank Sta=4979.5,4983.5
Exp/Cntr=0.3,0.1

Type RM Length L Ch R = 1,5000,500,500,500
BEGIN DESCRIPTION:
HICKORY28 10.0
END DESCRIPTION:
XS GIS Cut Line= 3
      2737420.39     10188306.20      2737101.08     10187190.28
      2736980.42     10186663.22
#Sta/Elev= 30
  3839.3 1343.57  3872.2 1342.69  3932.9 1341.99  4061.2 1341.11  4112.9 1340.86
  4209.4 1336.75  4235.1 1335.29  4300.2 1330.60  4313.3 1332.94  4331.4 1333.36
  4435.4 1334.43  4453.6 1333.84  4671.9 1337.87  4783.6 1337.47  4817.4 1335.40
  4868.8 1333.97  4968.1 1332.58  4993.9 1330.23  4994.2 1329.73  4997.9 1330.23
  5000.0 1330.23  5017.6 1336.71  5044.5 1336.35  5099.7 1336.13  5171.5 1337.68
  5221.7 1341.16  5253.6 1345.77  5335.6 1349.58  5438.2 1349.87  5540.7 1352.52
#Mann=10,-1,0
  3839.3    0.12       0  3872.2    0.05       0  3932.9    0.12       0
  4061.2    0.05       0  4209.4    0.12       0  4235.1    0.05       0
  4868.8    0.12       0  4993.9    0.07       0  4997.9    0.12       0
  5044.5    0.05       0
Bank Sta=4993.9,4997.9
Exp/Cntr=0.3,0.1

Type RM Length L Ch R = 1,4500,500,500,500
BEGIN DESCRIPTION:
HICKORY28 9.0
END DESCRIPTION:
XS GIS Cut Line= 3
      2737528.21     10188306.23      2737504.49     10187066.46
      2737474.30     10186482.34
#Sta/Elev= 30
  3760.0 1343.79  3783.1 1344.24  3823.1 1342.32  3853.1 1343.01  3863.1 1341.77
  4063.7 1337.20  4234.5 1331.82  4283.2 1328.83  4333.2 1329.56  4353.2 1327.65
  4373.2 1329.91  4402.0 1330.34  4513.3 1333.52  4563.7 1332.30  4633.3 1331.08
  4753.3 1331.95  4933.3 1329.89  4963.3 1330.70  4991.3 1327.62  4991.6 1327.12
  4995.3 1327.62  5004.2 1327.80  5013.4 1330.10  5023.4 1335.74  5043.4 1342.50
  5063.4 1343.51  5253.7 1341.25  5443.9 1347.04  5544.1 1347.01  5584.9 1344.76
#Mann=7,-1,0
  3760.0    0.05       0  4063.7    0.12       0  4234.5    0.05       0
  4402.0    0.12       0  4563.7    0.05       0  4991.3    0.05       0
  4995.3    0.05       0
Bank Sta=4991.3,4995.3
Exp/Cntr=0.3,0.1

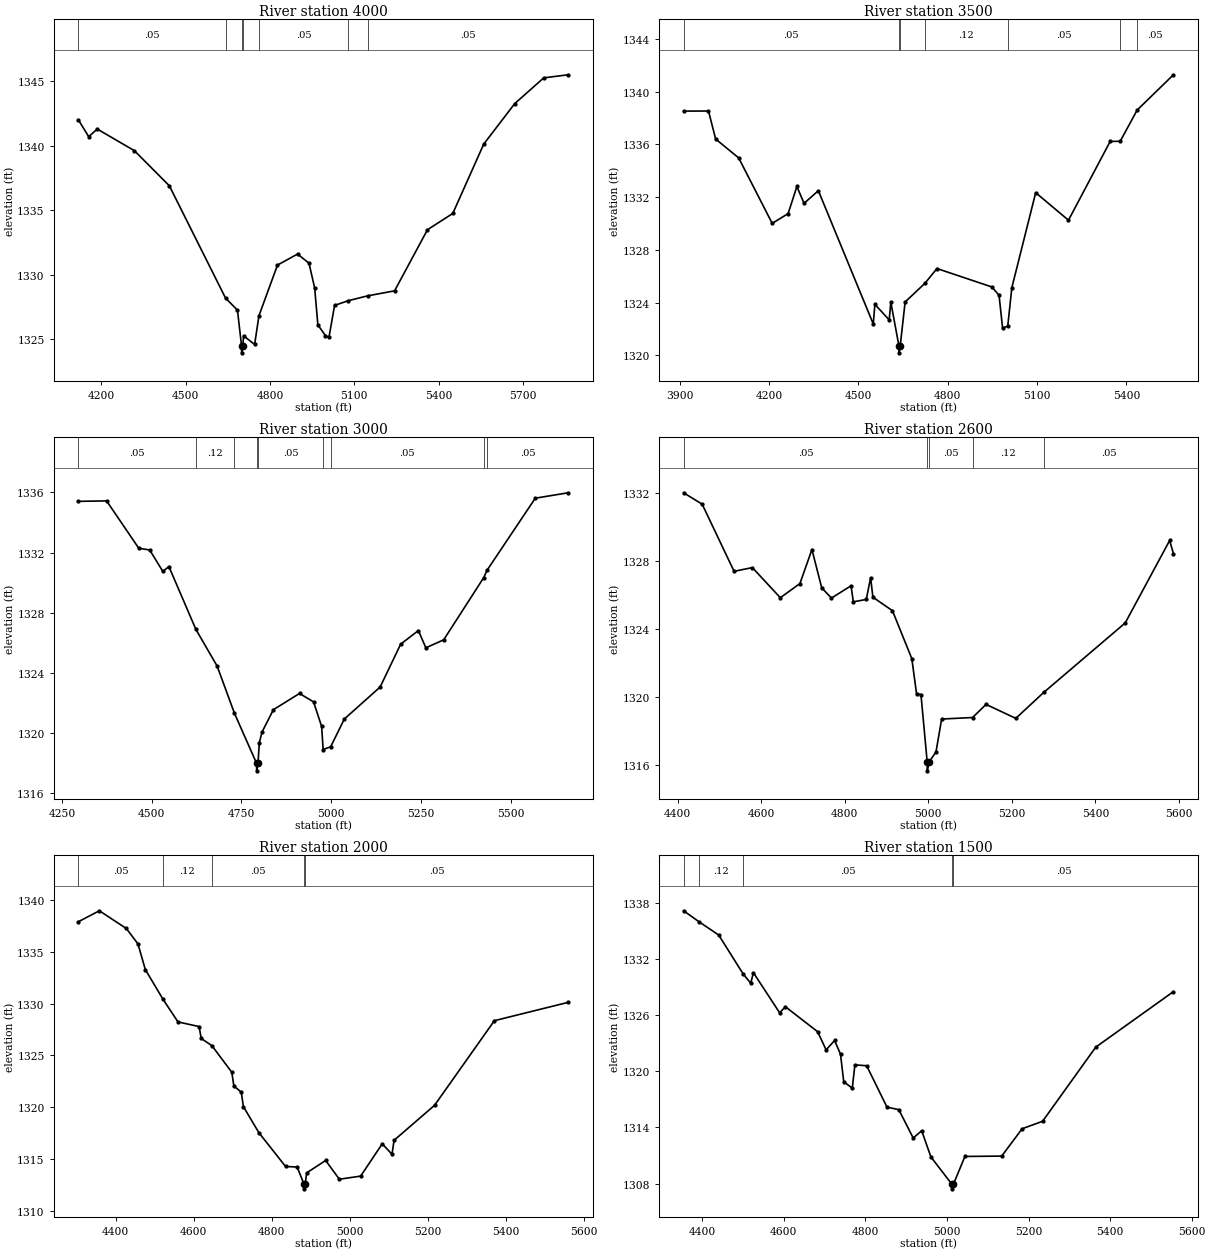
Type RM Length L Ch R = 1,4000,500,500,500
BEGIN DESCRIPTION:
HICKORY28 8.0
END DESCRIPTION:
XS GIS Cut Line= 3
      2737689.93     10188279.23      2737857.02     10187413.10
      2737905.69     10186553.07
#Sta/Elev= 30
  4117.9 1342.03  4154.7 1340.72  4185.2 1341.31  4317.6 1339.63  4441.8 1336.91
  4641.8 1328.20  4684.3 1327.26  4699.1 1324.45  4699.3 1323.95  4703.1 1324.45
  4706.2 1325.27  4745.4 1324.60  4760.8 1326.83  4826.8 1330.76  4898.1 1331.61
  4938.9 1330.91  4959.2 1328.97  4970.5 1326.12  4997.4 1325.29  5010.0 1325.15
  5030.0 1327.63  5079.5 1328.00  5147.4 1328.37  5243.6 1328.76  5360.6 1333.50
  5450.7 1334.76  5560.9 1340.14  5671.1 1343.28  5774.5 1345.28  5861.4 1345.52
#Mann=7,-1,0
  4117.9    0.05       0  4641.8    0.12       0  4699.1    0.05       0
  4703.1    0.12       0  4760.8    0.05       0  5079.5    0.12       0
  5147.4    0.05       0
Bank Sta=4699.1,4703.1
Exp/Cntr=0.3,0.1

Type RM Length L Ch R = 1,3500,500,500,500
BEGIN DESCRIPTION:
HICKORY28 7.0
END DESCRIPTION:
XS GIS Cut Line= 3
      2737878.59     10188324.19      2738289.46     10187318.48
      2738282.91     10186760.82
#Sta/Elev= 30
  3913.6 1338.53  3997.1 1338.54  4021.1 1336.41  4098.4 1334.98  4210.9 1330.01
  4264.4 1330.75  4293.8 1332.81  4317.8 1331.53  4365.9 1332.49  4550.2 1322.37
  4555.6 1323.86  4603.7 1322.68  4609.1 1324.03  4636.5 1320.68  4636.8 1320.18
  4640.5 1320.68  4657.1 1324.04  4723.6 1325.46  4764.0 1326.58  4948.4 1325.18
  4972.4 1324.55  4984.2 1322.07  5001.5 1322.20  5015.4 1325.13  5095.4 1332.34
  5205.4 1330.25  5345.4 1336.23  5379.0 1336.24  5436.0 1338.61  5557.7 1341.29
#Mann=7,-1,0
  3913.6    0.05       0  4636.5    0.07       0  4640.5    0.05       0
  4723.6    0.12       0  5001.5    0.05       0  5379.0    0.12       0
  5436.0    0.05       0
Bank Sta=4636.5,4640.5
Exp/Cntr=0.3,0.1

Type RM Length L Ch R = 1,3000,400,400,400
BEGIN DESCRIPTION:
HICKORY28 6.0
END DESCRIPTION:
XS GIS Cut Line= 3
      2738246.98     10188261.26      2738560.58     10187630.86
      2738991.72     10187130.34
#Sta/Elev= 30
  4295.9 1335.41  4374.6 1335.44  4464.2 1332.29  4494.9 1332.17  4531.4 1330.74
  4548.2 1331.07  4623.5 1326.88  4682.5 1324.45  4730.9 1321.30  4792.5 1317.97
  4792.8 1317.47  4796.5 1317.97  4800.1 1319.33  4807.6 1320.05  4839.3 1321.54
  4912.1 1322.62  4951.3 1322.06  4973.7 1320.43  4978.0 1318.89  4998.9 1319.07
  5037.0 1320.92  5136.8 1323.05  5193.9 1325.90  5243.3 1326.81  5264.1 1325.66
  5313.8 1326.19  5425.6 1330.34  5434.3 1330.81  5569.1 1335.62  5660.6 1335.98
#Mann=9,-1,0
  4295.9    0.05       0  4623.5    0.12       0  4730.9    0.05       0
  4792.5    0.05       0  4796.5    0.05       0  4978.0    0.12       0
  4998.9    0.05       0  5425.6    0.12       0  5434.3    0.05       0
Bank Sta=4792.5,4796.5
Exp/Cntr=0.3,0.1

Type RM Length L Ch R = 1,2600,600,600,600
BEGIN DESCRIPTION:
HICKORY28 5.0
END DESCRIPTION:
XS GIS Cut Line= 3
      2738489.56     10188503.84      2738724.00     10187967.00
      2739109.47     10187524.56
#Sta/Elev= 30
  4414.2 1332.00  4458.6 1331.33  4535.0 1327.39  4578.7 1327.61  4645.7 1325.84
  4692.6 1326.67  4721.4 1328.67  4744.8 1326.42  4768.2 1325.82  4815.0 1326.54
  4820.5 1325.60  4851.5 1325.74  4861.9 1327.02  4867.3 1325.87  4914.1 1325.08
  4960.6 1322.26  4971.8 1320.21  4982.4 1320.16  4997.4 1316.18  4997.6 1315.68
  5001.4 1316.18  5018.4 1316.79  5031.9 1318.72  5106.0 1318.81  5138.2 1319.58
  5209.4 1318.76  5276.7 1320.29  5471.4 1324.36  5577.8 1329.20  5586.8 1328.43
#Mann=5,-1,0
  4414.2    0.05       0  4997.4    0.03       0  5001.4    0.05       0
  5106.0    0.12       0  5276.7    0.05       0
Bank Sta=4997.4,5001.4
Exp/Cntr=0.3,0.1

Type RM Length L Ch R = 1,2000,500,500,500
BEGIN DESCRIPTION:
HICKORY28 4.0
END DESCRIPTION:
XS GIS Cut Line= 3
      2738855.68     10188803.12      2739111.88     10188156.53
      2739307.17     10187632.32
#Sta/Elev= 30
  4304.5 1337.91  4358.3 1338.97  4427.4 1337.26  4457.1 1335.78  4476.1 1333.29
  4521.2 1330.43  4559.8 1328.23  4613.9 1327.78  4619.3 1326.63  4646.8 1325.93
  4697.6 1323.37  4703.0 1322.04  4722.0 1321.44  4727.3 1320.05  4767.0 1317.53
  4835.4 1314.26  4865.1 1314.21  4882.1 1312.60  4882.3 1312.10  4886.1 1312.60
  4889.4 1313.64  4938.1 1314.84  4973.2 1313.03  5027.8 1313.33  5083.1 1316.45
  5108.1 1315.44  5113.4 1316.79  5217.1 1320.17  5370.4 1328.35  5559.4 1330.12
#Mann=5,-1,0
  4304.5    0.05       0  4521.2    0.12       0  4646.8    0.05       0
  4882.1    0.03       0  4886.1    0.05       0
Bank Sta=4882.1,4886.1
Exp/Cntr=0.3,0.1

Type RM Length L Ch R = 1,1500,500,500,500
BEGIN DESCRIPTION:
HICKORY28 3.0
END DESCRIPTION:
XS GIS Cut Line= 3
      2738955.66     10188803.13      2739465.67     10188406.95
      2739505.69     10187853.10
#Sta/Elev= 30
  4354.2 1337.15  4392.1 1335.97  4440.2 1334.56  4499.9 1330.42  4518.8 1329.41
  4525.3 1330.54  4589.5 1326.26  4604.0 1326.89  4682.8 1324.23  4703.6 1322.29
  4724.4 1323.29  4738.9 1321.83  4746.8 1318.89  4767.8 1318.19  4774.2 1320.69
  4803.1 1320.59  4852.9 1316.17  4881.9 1315.90  4917.2 1312.87  4938.0 1313.65
  4960.6 1310.85  5011.9 1307.94  5012.1 1307.44  5015.9 1307.94  5044.0 1310.90
  5134.2 1310.94  5184.3 1313.86  5234.5 1314.66  5364.8 1322.58  5555.3 1328.51
#Mann=5,-1,0
  4354.2    0.05       0  4392.1    0.12       0  4499.9    0.05       0
  5011.9    0.03       0  5015.9    0.05       0
Bank Sta=5011.9,5015.9
Exp/Cntr=0.3,0.1

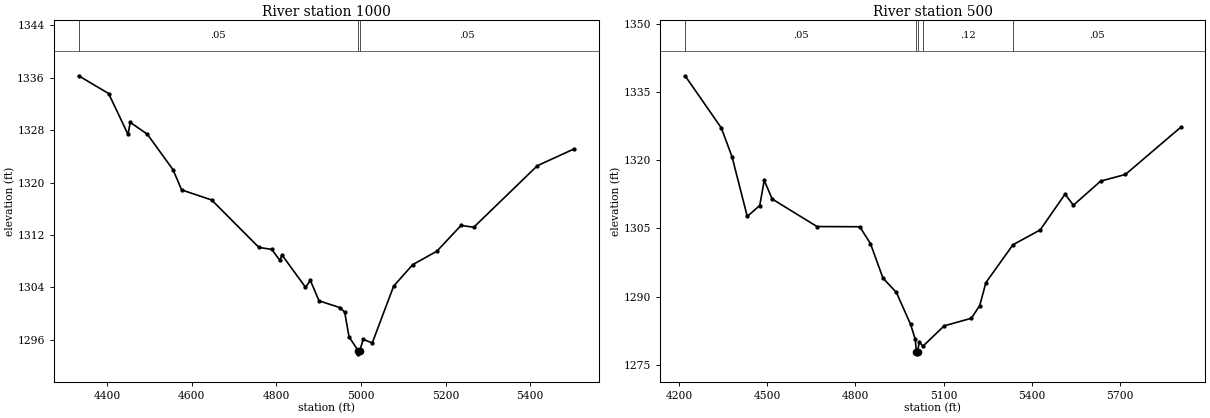
Type RM Length L Ch R = 1,1000,500,500,500
BEGIN DESCRIPTION:
HICKORY28 2.0
END DESCRIPTION:
XS GIS Cut Line= 3
      2739801.32     10188953.03      2739911.75     10188295.44
      2739631.73     10187876.62
#Sta/Elev= 30
  4333.2 1336.29  4404.1 1333.58  4449.9 1327.34  4455.0 1329.19  4495.4 1327.38
  4556.2 1321.96  4576.5 1318.88  4647.5 1317.34  4759.0 1310.11  4789.4 1309.80
  4808.5 1308.14  4813.6 1308.95  4869.1 1304.03  4880.7 1305.06  4901.0 1301.96
  4951.7 1300.90  4961.8 1300.20  4971.9 1296.47  4993.4 1294.37  4993.7 1293.87
  4997.4 1294.37  5005.4 1296.07  5026.9 1295.54  5077.4 1304.21  5122.5 1307.48
  5179.5 1309.53  5236.6 1313.46  5266.6 1313.18  5416.8 1322.57  5503.8 1325.14
#Mann=3,-1,0
  4333.2    0.05       0  4993.4    0.03       0  4997.4    0.05       0
Bank Sta=4993.4,4997.4
Exp/Cntr=0.3,0.1

Type RM Length L Ch R = 1,500,0,0,0
BEGIN DESCRIPTION:
HICKORY28 1.0
END DESCRIPTION:
XS GIS Cut Line= 3
      2739936.07     10188944.11      2740350.16     10188282.52
      2739649.65     10187705.11
#Sta/Elev= 30
  4219.5 1338.57  4342.9 1327.10  4379.5 1320.74  4431.3 1307.64  4473.8 1310.03
  4489.1 1315.56  4516.2 1311.47  4669.0 1305.41  4814.5 1305.37  4851.0 1301.67
  4893.5 1294.09  4939.4 1290.92  4987.8 1283.89  5003.5 1280.64  5007.6 1277.92
  5007.9 1277.42  5011.6 1277.92  5017.5 1280.09  5029.4 1279.08  5102.1 1283.57
  5194.7 1285.24  5223.3 1288.03  5244.2 1293.07  5336.6 1301.41  5429.2 1304.67
  5513.9 1312.53  5542.5 1310.11  5635.1 1315.40  5719.7 1316.87  5907.8 1327.23
#Mann=5,-1,0
  4219.5    0.05       0  5007.6    0.05       0  5011.6    0.05       0
  5029.4    0.12       0  5336.6    0.05       0
Bank Sta=5007.6,5011.6
Exp/Cntr=0.3,0.1

Chan Stop Cuts=-1