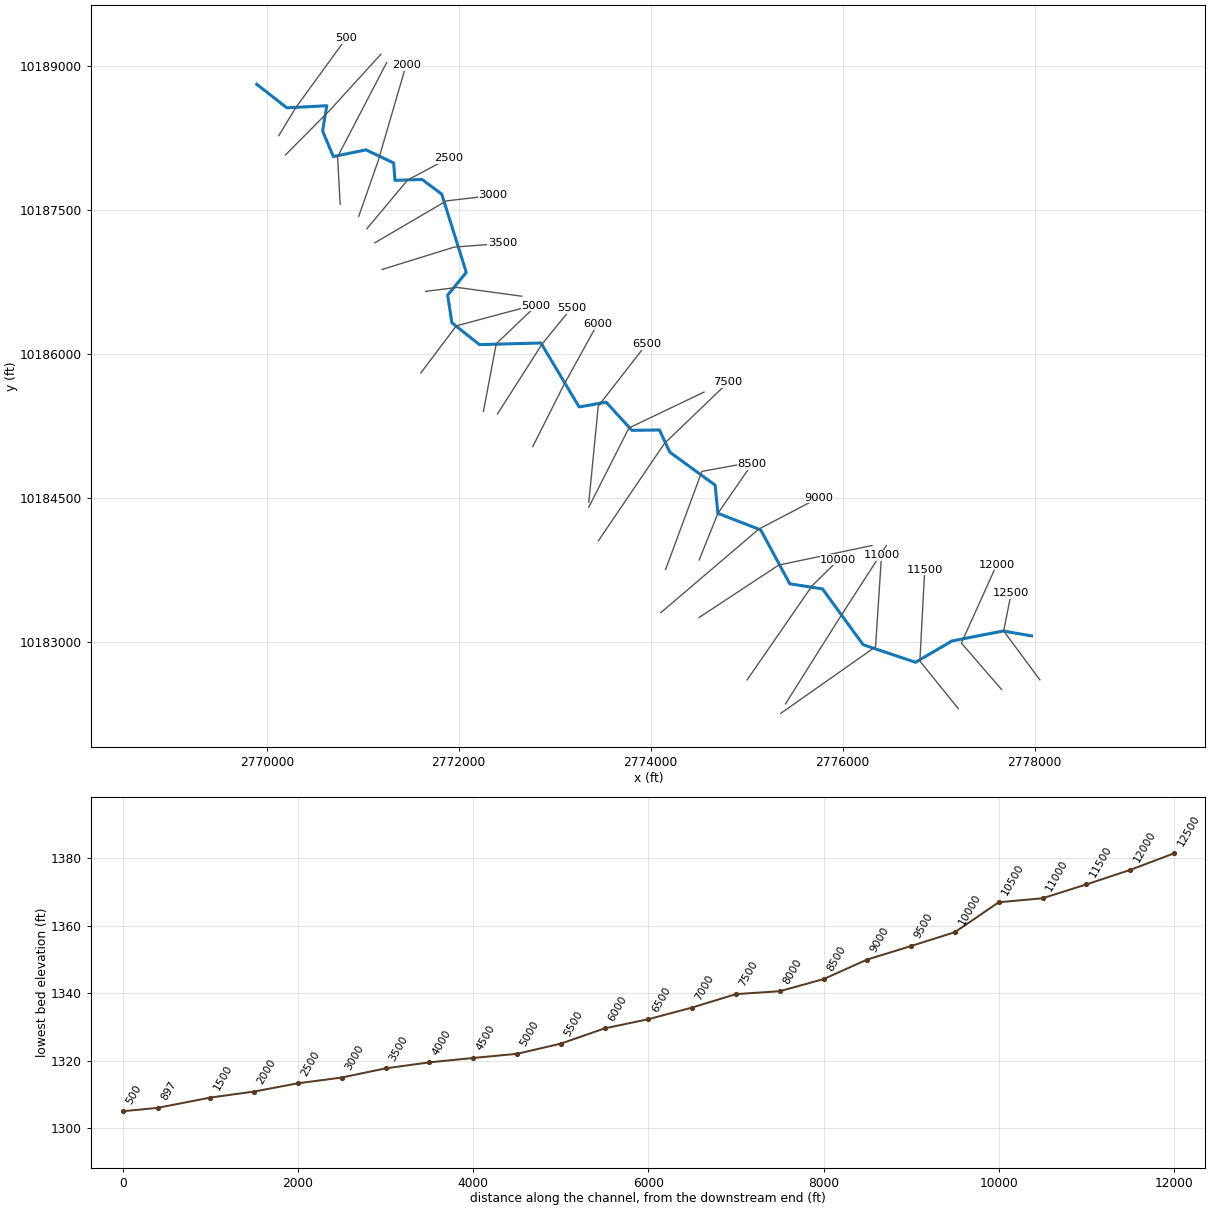
--- HICKORY30.prj (project) ---

Proj Title=HICKORY30 Base Level Engineering
Current Plan=p01
Default Exp/Contr=0.3,0.1
English Units
Geom File=g01
Flow File=f01
Plan File=p01
BEGIN DESCRIPTION:
HICKORY30
END DESCRIPTION:

--- HICKORY30.p01 (plan) ---

Plan Title=Multiple Run
Short Identifier=Multiple
Geom File=g01
Flow File=f01
Subcritical Flow
K Sum by GR= 0
Std Step Tol= 0.01
Critical Tol= 0.01
Num of Std Step Trials= 20
Max Error Tol= 0.3
Flow Tol Ratio= 0.001
Split Flow NTrial= 30
Split Flow Tol= 0.02
Split Flow Ratio= 0.02
Log Output Level= 0
Friction Slope Method= 1
Unsteady Friction Slope Method= 2
Unsteady Bridges Friction Slope Method= 1
Parabolic Critical Depth
Global Vel Dist=  1 , 1 , 1
Global Log Level= 0
CheckData=True
Encroach Param= -1, 0, 0, 0
BEGIN DESCRIPTION:
Multiple Run
END DESCRIPTION:

--- HICKORY30.f01 (steady flow) ---

Flow Title=Multiple
Number of Profiles=7
Profile Names=10-year,25-year,50-year,1pct_min,100-year,1pct_plu,500-year
River Rch & RM= HICKORY30,Reach-1,12500
     413     664     778     582    1015    1770    1365
River Rch & RM= HICKORY30,Reach-1,4500
     538     886     957     667    1252    2352    1676
River Rch & RM= HICKORY30,Reach-1,897
     733    1223    1446    1034    1919    3562    2561
Boundary for River Rch & Prof#=HICKORY30,Reach-1,1
Up Type=0
Dn Type=3
Dn Slope=0.005
Boundary for River Rch & Prof#=HICKORY30,Reach-1,2
Up Type=0
Dn Type=3
Dn Slope=0.005
Boundary for River Rch & Prof#=HICKORY30,Reach-1,3
Up Type=0
Dn Type=3
Dn Slope=0.005
Boundary for River Rch & Prof#=HICKORY30,Reach-1,4
Up Type=0
Dn Type=3
Dn Slope=0.005
Boundary for River Rch & Prof#=HICKORY30,Reach-1,5
Up Type=0
Dn Type=3
Dn Slope=0.005
Boundary for River Rch & Prof#=HICKORY30,Reach-1,6
Up Type=0
Dn Type=3
Dn Slope=0.005
Boundary for River Rch & Prof#=HICKORY30,Reach-1,7
Up Type=0
Dn Type=3
Dn Slope=0.005

--- HICKORY30.g01 (geometry) ---

Geom Title=Existing Conditions

River Reach=HICKORY30,Reach-1
Reach XY= 30
      2777969.75     10183061.00      2777673.00     10183112.00
      2777139.25     10183008.00      2776760.50     10182786.00
      2776214.25     10182969.00      2775790.50     10183551.00
      2775449.75     10183604.00      2775147.00     10184166.00
      2774700.50     10184339.00      2774672.00     10184633.00
      2774200.50     10184976.00      2774091.25     10185208.00
      2773804.75     10185204.00      2773536.00     10185498.00
      2773254.75     10185448.00      2772857.00     10186115.00
      2772216.25     10186098.00      2771928.75     10186326.00
      2771885.00     10186614.00      2772078.75     10186851.00
      2771823.50     10187667.00      2771619.25     10187820.00
      2771336.00     10187811.00      2771322.50     10187992.00
      2771033.50     10188129.00      2770693.75     10188059.00
      2770581.75     10188326.00      2770625.50     10188589.00
      2770210.00     10188567.00      2769896.50     10188812.00

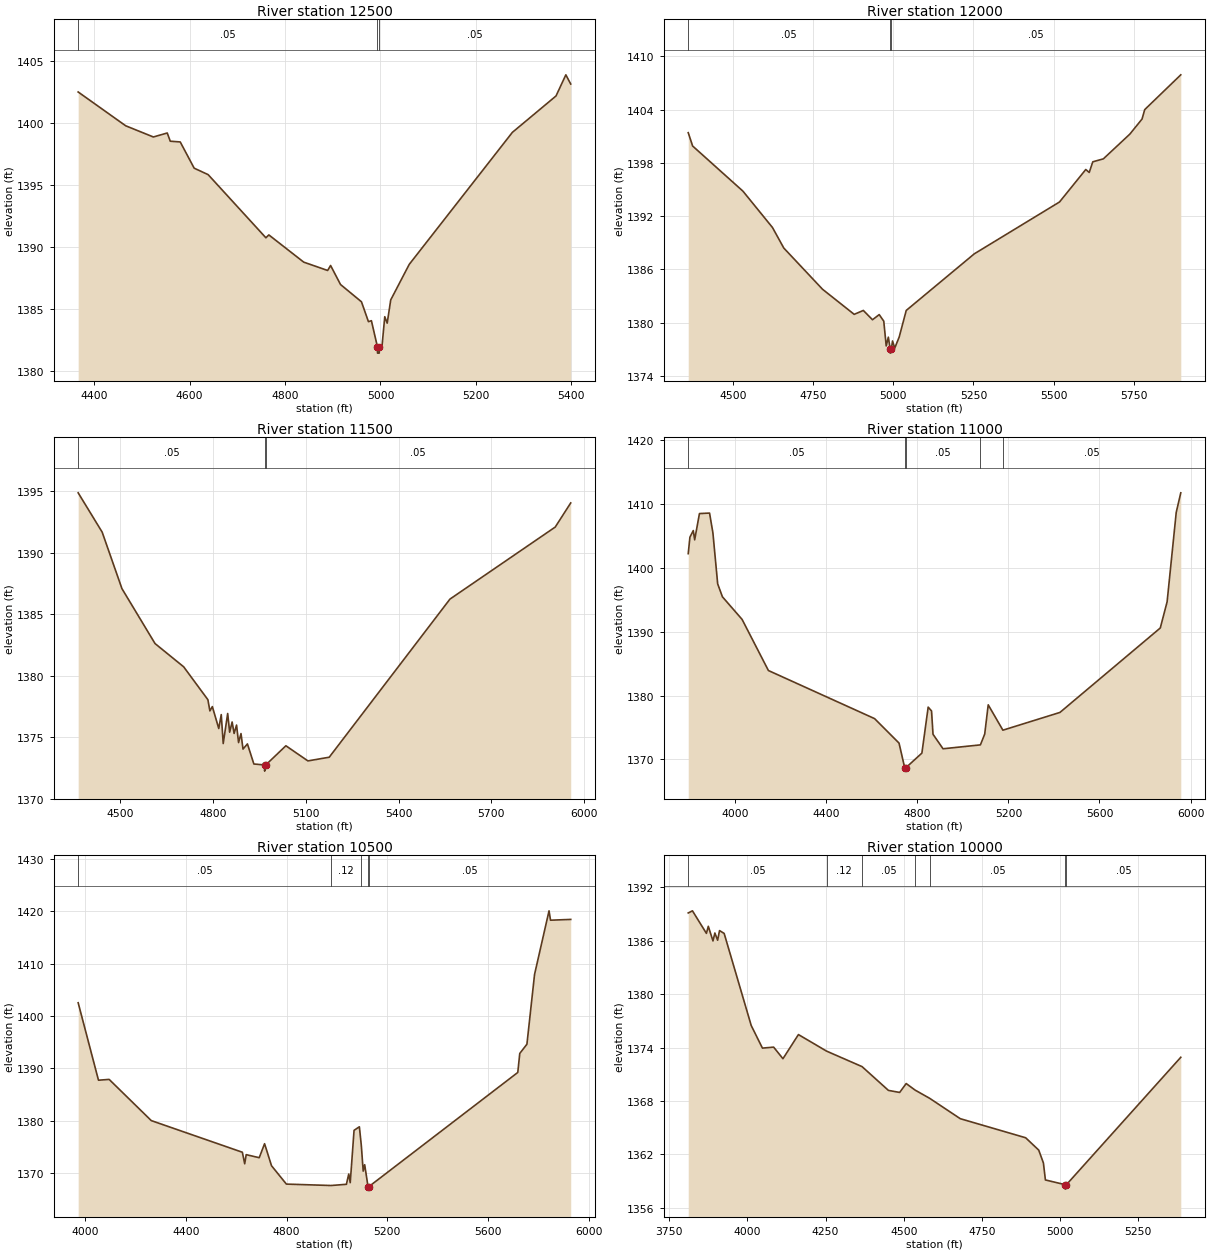
Type RM Length L Ch R = 1,12500,500,500,500
BEGIN DESCRIPTION:
HICKORY30 25.0
END DESCRIPTION:
XS GIS Cut Line= 3
      2778055.69     10182603.10      2777678.40     10183112.00
      2777755.69     10183503.14
#Sta/Elev= 30
  4366.5 1402.47  4466.1 1399.75  4524.1 1398.85  4553.2 1399.17  4559.5 1398.51
  4580.4 1398.45  4609.6 1396.34  4638.9 1395.82  4759.9 1390.74  4766.1 1390.97
  4839.2 1388.78  4889.3 1388.11  4895.5 1388.51  4916.3 1386.98  4960.2 1385.59
  4974.8 1383.99  4981.0 1384.07  4993.7 1381.96  4993.9 1381.46  4997.4 1381.46
  4997.7 1381.96  5003.1 1381.97  5009.0 1384.39  5014.1 1383.87  5021.5 1385.74
  5060.3 1388.60  5276.4 1399.22  5367.9 1402.15  5388.5 1403.85  5398.7 1403.11
#Mann=3,-1,0
  4366.5    0.05       0  4993.7    0.05       0  4997.7    0.05       0
Bank Sta=4993.7,4997.7
Exp/Cntr=0.3,0.1

Type RM Length L Ch R = 1,12000,500,500,500
BEGIN DESCRIPTION:
HICKORY30 24.0
END DESCRIPTION:
XS GIS Cut Line= 3
      2777655.67     10182503.12      2777237.68     10182986.18
      2777605.69     10183803.12
#Sta/Elev= 30
  4361.2 1401.40  4374.9 1399.90  4531.7 1394.81  4623.8 1390.71  4659.0 1388.40
  4779.6 1383.76  4878.3 1380.93  4906.8 1381.37  4935.4 1380.32  4956.3 1380.90
  4970.5 1380.16  4978.1 1377.37  4984.7 1378.36  4990.4 1377.06  4990.6 1376.56
  4994.4 1377.06  4997.7 1377.93  5004.7 1377.13  5018.6 1378.38  5040.5 1381.37
  5252.6 1387.75  5518.1 1393.59  5599.9 1397.25  5610.7 1396.92  5621.8 1398.12
  5654.7 1398.45  5737.3 1401.24  5775.3 1402.94  5783.6 1404.00  5896.0 1407.92
#Mann=3,-1,0
  4361.2    0.05       0  4990.4    0.03       0  4994.4    0.05       0
Bank Sta=4990.4,4994.4
Exp/Cntr=0.3,0.1

Type RM Length L Ch R = 1,11500,500,500,500
BEGIN DESCRIPTION:
HICKORY30 23.0
END DESCRIPTION:
XS GIS Cut Line= 3
      2777205.68     10182303.11      2776805.25     10182797.48
      2776855.69     10183753.15
#Sta/Elev= 30
  4363.8 1394.86  4441.4 1391.67  4505.4 1387.08  4612.4 1382.62  4705.1 1380.73
  4783.4 1378.06  4789.9 1377.15  4797.8 1377.50  4818.6 1375.72  4826.6 1376.85
  4833.0 1374.50  4847.4 1376.94  4853.8 1375.42  4861.8 1376.25  4868.2 1375.32
  4876.1 1376.00  4882.6 1374.58  4890.5 1375.31  4897.0 1374.05  4911.3 1374.47
  4932.1 1372.84  4966.6 1372.76  4966.9 1372.26  4970.6 1372.76  5035.7 1374.32
  5106.9 1373.09  5175.9 1373.39  5566.4 1386.23  5906.9 1392.08  5957.0 1394.04
#Mann=3,-1,0
  4363.8    0.05       0  4966.6    0.05       0  4970.6    0.05       0
Bank Sta=4966.6,4970.6
Exp/Cntr=0.3,0.1

Type RM Length L Ch R = 1,11000,500,500,500
BEGIN DESCRIPTION:
HICKORY30 22.0
END DESCRIPTION:
XS GIS Cut Line= 3
      2775355.67     10182253.10      2776343.45     10182947.79
      2776405.68     10183903.07
#Sta/Elev= 30
  3792.4 1402.21  3799.8 1404.79  3814.6 1405.82  3820.7 1404.37  3841.7 1408.48
  3886.1 1408.56  3900.9 1405.45  3921.8 1397.48  3942.7 1395.45  4029.0 1391.92
  4144.8 1383.91  4611.5 1376.38  4718.9 1372.55  4744.0 1368.66  4744.2 1368.16
  4748.0 1368.66  4819.4 1370.98  4847.0 1378.18  4861.8 1377.58  4868.3 1373.93
  4912.3 1371.66  5076.6 1372.27  5095.5 1373.96  5110.9 1378.54  5175.4 1374.57
  5426.2 1377.35  5867.2 1390.57  5897.2 1394.67  5937.3 1408.68  5957.3 1411.73
#Mann=5,-1,0
  3792.4    0.05       0  4744.0    0.03       0  4748.0    0.05       0
  5076.6    0.12       0  5175.4    0.05       0
Bank Sta=4744,4748
Exp/Cntr=0.3,0.1

Type RM Length L Ch R = 1,10500,500,500,500
BEGIN DESCRIPTION:
HICKORY30 21.0
END DESCRIPTION:
XS GIS Cut Line= 3
      2775405.69     10182353.12      2775952.50     10183223.03
      2776455.69     10184003.12
#Sta/Elev= 30
  3972.5 1402.54  4053.2 1387.76  4095.6 1387.91  4262.8 1380.05  4624.4 1374.01
  4633.8 1371.81  4639.7 1373.55  4691.5 1372.97  4712.7 1375.64  4740.2 1371.44
  4799.3 1367.93  4976.6 1367.66  5037.6 1367.89  5046.9 1369.85  5052.8 1368.20
  5068.0 1378.19  5089.1 1378.87  5096.7 1375.37  5104.3 1370.41  5110.2 1371.63
  5123.4 1367.47  5123.7 1366.97  5127.4 1367.47  5718.1 1389.24  5726.0 1392.87
  5754.4 1394.63  5784.7 1407.95  5842.2 1420.09  5848.1 1418.30  5928.3 1418.45
#Mann=5,-1,0
  3972.5    0.05       0  4976.6    0.12       0  5096.7    0.05       0
  5123.4    0.07       0  5127.4    0.05       0
Bank Sta=5123.4,5127.4
Exp/Cntr=0.3,0.1

Type RM Length L Ch R = 1,10000,500,500,500
BEGIN DESCRIPTION:
HICKORY30 20.0
END DESCRIPTION:
XS GIS Cut Line= 3
      2775005.68     10182603.11      2775681.15     10183581.74
      2775955.67     10183853.10
#Sta/Elev= 30
  3810.9 1389.13  3824.4 1389.37  3869.0 1386.84  3875.1 1387.63  3890.0 1385.99
  3896.1 1386.88  3904.9 1386.07  3911.0 1387.15  3925.8 1386.83  4012.4 1376.48
  4048.2 1373.95  4084.0 1374.06  4113.8 1372.76  4163.3 1375.47  4253.4 1373.61
  4366.8 1371.87  4451.1 1369.20  4487.0 1368.97  4507.9 1369.97  4536.1 1369.24
  4582.9 1368.31  4681.0 1366.02  4889.9 1363.88  4931.8 1362.49  4946.7 1361.05
  4953.1 1359.14  5016.3 1358.61  5016.6 1358.11  5020.3 1358.61  5386.0 1372.92
#Mann=7,-1,0
  3810.9    0.05       0  4253.4    0.12       0  4366.8    0.05       0
  4536.1    0.12       0  4582.9    0.05       0  5016.3    0.03       0
  5020.3    0.05       0
Bank Sta=5016.3,5020.3
Exp/Cntr=0.3,0.1

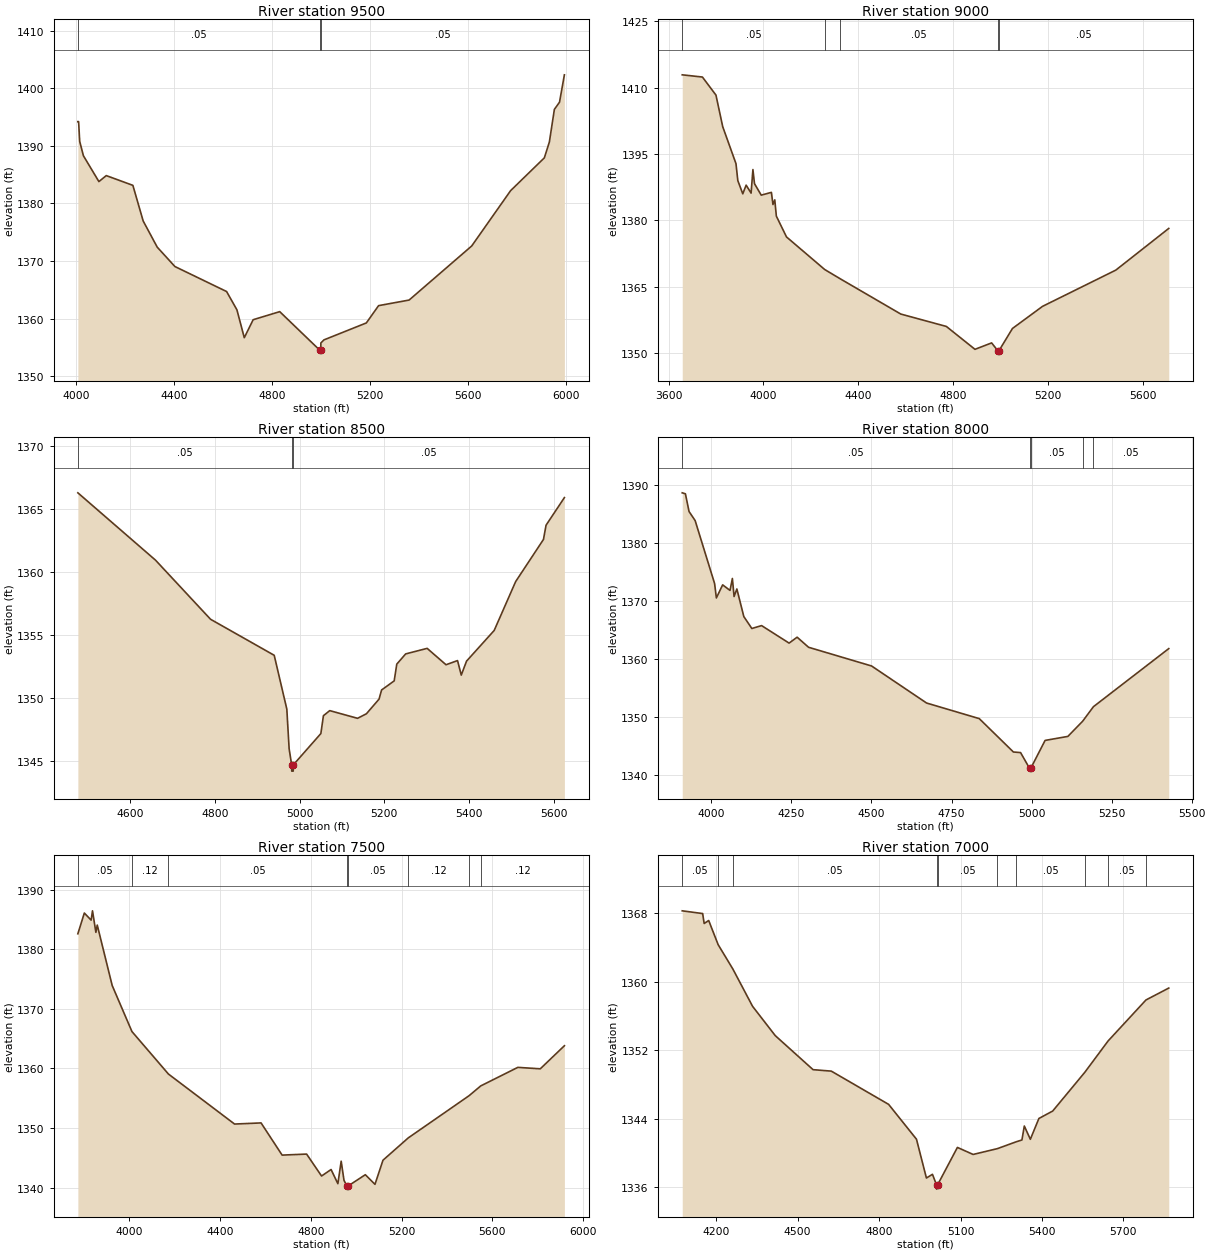
Type RM Length L Ch R = 1,9500,500,500,500
BEGIN DESCRIPTION:
HICKORY30 19.0
END DESCRIPTION:
XS GIS Cut Line= 3
      2774505.68     10183253.11      2775334.36     10183799.32
      2776305.71     10184003.12
#Sta/Elev= 30
  4007.5 1394.19  4010.5 1394.19  4015.0 1390.75  4030.1 1388.27  4093.3 1383.78
  4123.4 1384.82  4231.9 1383.13  4274.0 1376.94  4331.2 1372.41  4403.4 1369.04
  4614.3 1364.70  4656.4 1361.53  4686.5 1356.69  4722.7 1359.81  4831.1 1361.21
  4994.7 1354.51  4994.9 1354.01  4998.7 1354.51  4998.9 1355.77  5011.6 1356.31
  5184.5 1359.25  5234.4 1362.25  5359.0 1363.22  5614.4 1372.61  5773.1 1382.21
  5910.7 1387.90  5931.2 1390.65  5951.6 1396.31  5972.6 1397.56  5992.5 1402.31
#Mann=3,-1,0
  4007.5    0.05       0  4994.7    0.03       0  4998.7    0.05       0
Bank Sta=4994.7,4998.7
Exp/Cntr=0.3,0.1

Type RM Length L Ch R = 1,9000,500,500,500
BEGIN DESCRIPTION:
HICKORY30 18.0
END DESCRIPTION:
XS GIS Cut Line= 3
      2774105.68     10183303.11      2775126.75     10184174.43
      2775755.65     10184503.09
#Sta/Elev= 30
  3657.7 1412.90  3742.8 1412.40  3799.9 1408.32  3828.4 1401.19  3884.4 1392.82
  3892.1 1389.00  3913.0 1386.01  3927.2 1387.97  3948.1 1386.17  3955.8 1391.49
  3962.4 1388.30  3990.9 1385.71  4033.7 1386.34  4040.3 1383.59  4048.0 1384.64
  4054.6 1380.97  4097.4 1376.27  4258.6 1368.90  4324.6 1366.79  4579.4 1358.84
  4771.6 1356.04  4892.3 1350.87  4962.6 1352.32  4989.1 1350.51  4989.4 1350.01
  4993.1 1350.51  5050.4 1355.58  5177.2 1360.58  5486.3 1368.77  5709.6 1378.19
#Mann=5,-1,0
  3657.7    0.05       0  4258.6    0.12       0  4324.6    0.05       0
  4989.1    0.05       0  4993.1    0.05       0
Bank Sta=4989.1,4993.1
Exp/Cntr=0.3,0.1

Type RM Length L Ch R = 1,8500,500,500,500
BEGIN DESCRIPTION:
HICKORY30 17.0
END DESCRIPTION:
XS GIS Cut Line= 3
      2774505.68     10183853.11      2774700.85     10184338.65
      2775055.71     10184853.14
#Sta/Elev= 30
  4476.7 1366.28  4659.9 1360.94  4789.8 1356.25  4940.1 1353.39  4969.9 1349.12
  4975.3 1345.98  4981.3 1344.70  4981.5 1344.20  4985.0 1344.20  4985.3 1344.70
  5050.2 1347.18  5056.3 1348.60  5071.2 1349.00  5136.8 1348.39  5157.7 1348.75
  5187.5 1349.91  5193.6 1350.64  5223.3 1351.36  5229.4 1352.69  5250.4 1353.50
  5301.1 1353.94  5345.6 1352.64  5372.8 1352.97  5381.6 1351.82  5394.1 1352.93
  5459.3 1355.36  5510.0 1359.24  5575.6 1362.58  5581.7 1363.71  5625.0 1365.90
#Mann=3,-1,0
  4476.7    0.05       0  4981.3    0.05       0  4985.3    0.05       0
Bank Sta=4981.3,4985.3
Exp/Cntr=0.3,0.1

Type RM Length L Ch R = 1,8000,500,500,500
BEGIN DESCRIPTION:
HICKORY30 16.0
END DESCRIPTION:
XS GIS Cut Line= 3
      2774155.69     10183753.13      2774534.09     10184776.30
      2774955.65     10184853.10
#Sta/Elev= 30
  3909.1 1388.63  3919.0 1388.46  3930.4 1385.40  3949.4 1383.84  4010.2 1372.97
  4015.7 1370.49  4035.3 1372.75  4058.3 1371.79  4065.7 1373.85  4071.0 1370.74
  4079.7 1372.04  4101.4 1367.28  4126.5 1365.22  4156.9 1365.72  4242.8 1362.70
  4267.9 1363.72  4303.6 1361.98  4500.5 1358.75  4672.2 1352.36  4836.7 1349.67
  4943.3 1343.91  4965.7 1343.81  4993.6 1341.11  4993.9 1340.61  4997.6 1341.11
  5042.3 1345.91  5113.4 1346.60  5159.4 1349.21  5193.3 1351.73  5428.5 1361.75
#Mann=5,-1,0
  3909.1    0.05       0  4993.6    0.05       0  4997.6    0.05       0
  5159.4    0.12       0  5193.3    0.05       0
Bank Sta=4993.6,4997.6
Exp/Cntr=0.3,0.1

Type RM Length L Ch R = 1,7500,500,500,500
BEGIN DESCRIPTION:
HICKORY30 15.0
END DESCRIPTION:
XS GIS Cut Line= 3
      2773455.66     10184053.07      2774143.86     10185067.57
      2774805.71     10185703.14
#Sta/Elev= 30
  3774.1 1382.60  3802.6 1386.08  3832.5 1384.89  3838.6 1386.45  3853.5 1382.84
  3859.5 1384.06  3925.4 1373.91  4012.4 1366.19  4173.2 1359.06  4464.5 1350.67
  4581.2 1350.86  4674.0 1345.46  4781.9 1345.63  4847.7 1341.95  4889.7 1343.04
  4919.6 1340.66  4934.2 1344.44  4946.6 1341.23  4959.6 1340.25  4959.8 1339.75
  4963.6 1340.25  5040.6 1342.17  5083.1 1340.55  5118.3 1344.60  5229.5 1348.34
  5497.8 1355.43  5549.0 1357.07  5712.4 1360.18  5811.4 1359.94  5917.6 1363.81
#Mann=8,-1,0
  3774.1    0.05       0  4012.4    0.12       0  4173.2    0.05       0
  4959.6    0.05       0  4963.6    0.05       0  5229.5    0.12       0
  5497.8    0.05       0  5549.0    0.12       0
Bank Sta=4959.6,4963.6
Exp/Cntr=0.3,0.1

Type RM Length L Ch R = 1,7000,500,500,500
BEGIN DESCRIPTION:
HICKORY30 14.0
END DESCRIPTION:
XS GIS Cut Line= 3
      2773355.66     10184403.07      2773773.46     10185228.57
      2774555.71     10185603.12
#Sta/Elev= 30
  4074.8 1368.27  4150.0 1367.95  4155.6 1366.79  4172.3 1367.14  4207.1 1364.32
  4261.4 1361.47  4333.9 1357.12  4417.4 1353.70  4556.8 1349.72  4624.0 1349.55
  4835.1 1345.67  4937.8 1341.60  4974.4 1337.07  4996.7 1337.50  5011.6 1336.27
  5011.8 1335.77  5015.6 1336.27  5088.6 1340.64  5146.6 1339.82  5236.1 1340.50
  5305.4 1341.30  5326.3 1341.51  5335.1 1343.14  5357.3 1341.59  5388.8 1344.02
  5439.7 1344.89  5557.9 1349.41  5643.7 1353.07  5783.3 1357.86  5867.3 1359.25
#Mann=10,-1,0
  4074.8    0.05       0  4207.1    0.12       0  4261.4    0.05       0
  5011.6    0.05       0  5015.6    0.05       0  5236.1    0.12       0
  5305.4    0.05       0  5557.9    0.12       0  5643.7    0.05       0
  5783.3    0.12       0
Bank Sta=5011.6,5015.6
Exp/Cntr=0.3,0.1

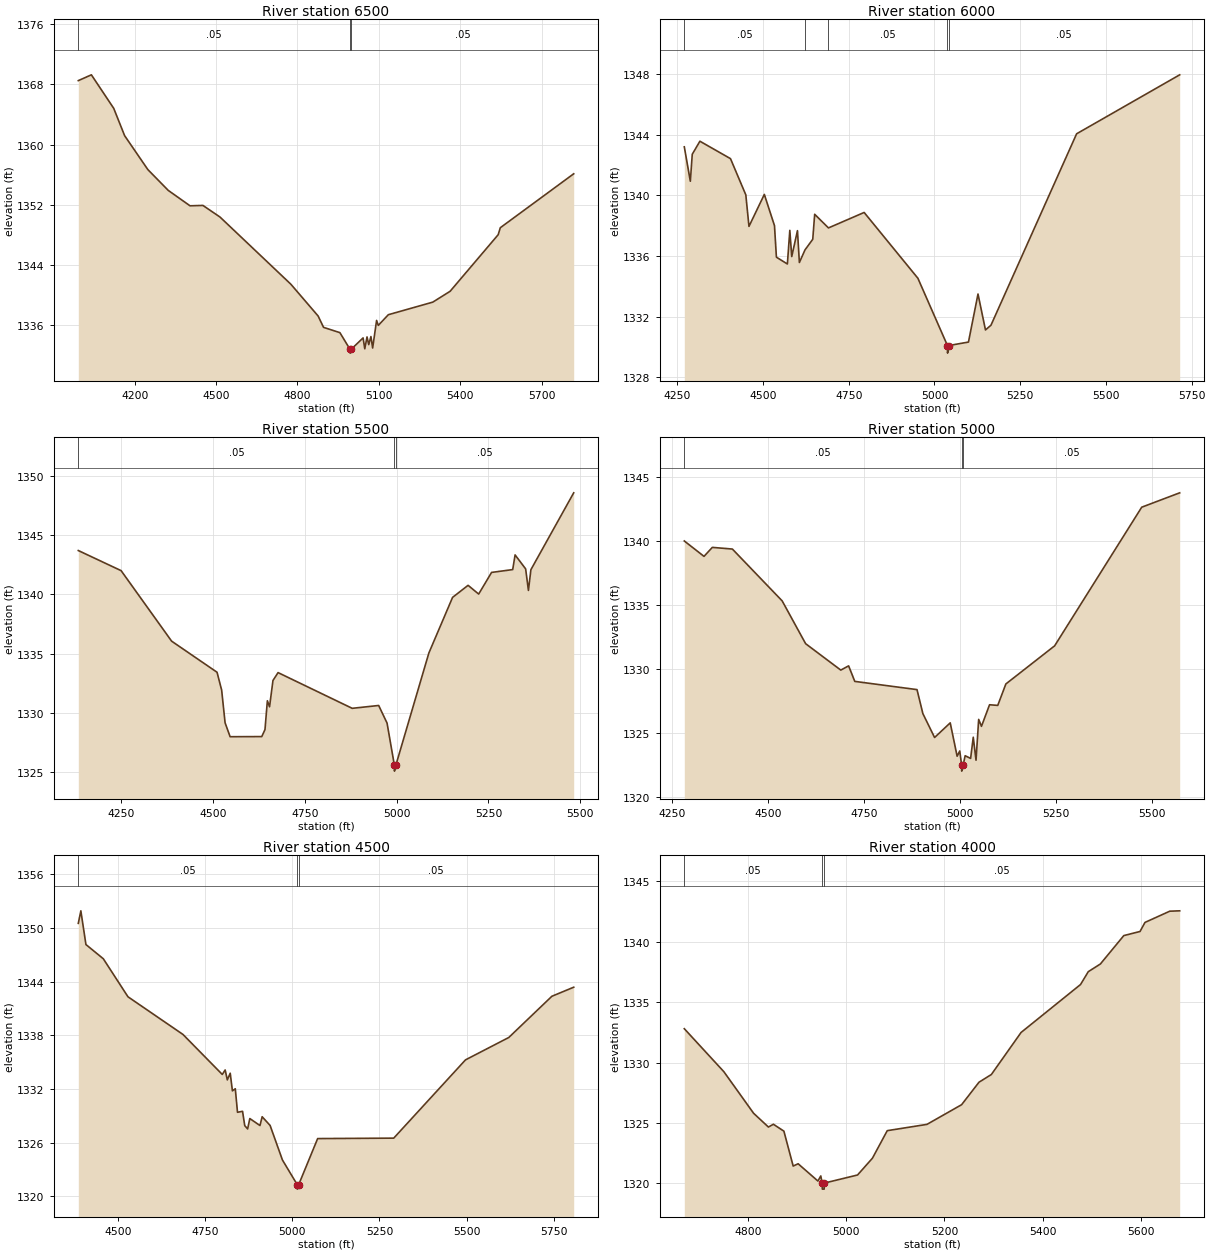
Type RM Length L Ch R = 1,6500,500,500,500
BEGIN DESCRIPTION:
HICKORY30 13.0
END DESCRIPTION:
XS GIS Cut Line= 3
      2773355.69     10184453.16      2773453.90     10185456.46
      2773955.68     10186103.11
#Sta/Elev= 30
  3991.9 1368.49  4040.1 1369.26  4122.5 1364.81  4162.7 1361.18  4248.3 1356.68
  4323.4 1353.92  4403.8 1351.87  4451.4 1351.92  4514.3 1350.38  4775.6 1341.46
  4876.1 1337.24  4896.2 1335.73  4956.4 1335.03  4993.8 1332.81  4994.1 1332.31
  4997.8 1332.81  5041.9 1334.33  5048.2 1332.89  5056.4 1334.46  5062.7 1333.44
  5070.8 1334.51  5077.2 1332.99  5091.7 1336.65  5098.0 1335.99  5135.0 1337.41
  5298.9 1339.08  5362.8 1340.52  5540.0 1348.03  5547.9 1348.96  5818.5 1356.12
#Mann=3,-1,0
  3991.9    0.05       0  4993.8    0.05       0  4997.8    0.05       0
Bank Sta=4993.8,4997.8
Exp/Cntr=0.3,0.1

Type RM Length L Ch R = 1,6000,500,500,500
BEGIN DESCRIPTION:
HICKORY30 12.0
END DESCRIPTION:
XS GIS Cut Line= 3
      2772771.68     10185034.63      2773099.69     10185686.23
      2773445.28     10186312.39
#Sta/Elev= 30
  4270.5 1343.20  4288.1 1340.93  4293.7 1342.71  4316.0 1343.57  4405.2 1342.42
  4449.9 1340.03  4459.1 1337.95  4503.9 1340.06  4533.5 1338.00  4539.1 1335.92
  4571.1 1335.47  4578.2 1337.69  4583.8 1335.96  4600.5 1337.67  4606.1 1335.57
  4622.5 1336.40  4645.1 1337.10  4650.7 1338.75  4690.9 1337.85  4795.0 1338.87
  4951.7 1334.53  5037.9 1330.09  5038.2 1329.59  5041.9 1330.09  5099.2 1330.32
  5127.0 1333.49  5148.8 1331.12  5164.8 1331.43  5414.6 1344.06  5715.2 1347.95
#Mann=5,-1,0
  4270.5    0.05       0  4622.5    0.12       0  4690.9    0.05       0
  5037.9    0.05       0  5041.9    0.05       0
Bank Sta=5037.9,5041.9
Exp/Cntr=0.3,0.1

Type RM Length L Ch R = 1,5500,500,500,500
BEGIN DESCRIPTION:
HICKORY30 11.0
END DESCRIPTION:
XS GIS Cut Line= 3
      2772403.61     10185374.89      2772869.62     10186105.05
      2773174.07     10186478.60
#Sta/Elev= 30
  4133.8 1343.71  4250.3 1342.01  4387.7 1336.05  4511.3 1333.42  4523.9 1331.91
  4533.2 1329.15  4546.9 1327.97  4633.0 1327.98  4641.8 1328.57  4648.3 1331.01
  4654.2 1330.50  4663.5 1332.72  4677.4 1333.39  4879.1 1330.37  4951.2 1330.61
  4974.0 1329.12  4993.9 1325.56  4994.1 1325.06  4997.9 1325.56  5087.8 1335.05
  5152.3 1339.75  5194.5 1340.77  5223.3 1340.03  5258.4 1341.86  5315.9 1342.10
  5322.4 1343.34  5351.1 1342.16  5358.7 1340.34  5365.4 1342.09  5481.9 1348.59
#Mann=3,-1,0
  4133.8    0.05       0  4993.9    0.05       0  4997.9    0.05       0
Bank Sta=4993.9,4997.9
Exp/Cntr=0.3,0.1

Type RM Length L Ch R = 1,5000,500,500,500
BEGIN DESCRIPTION:
HICKORY30 10.0
END DESCRIPTION:
XS GIS Cut Line= 3
      2772257.80     10185402.71      2772391.43     10186107.45
      2772805.65     10186503.08
#Sta/Elev= 30
  4282.7 1339.98  4334.0 1338.78  4355.7 1339.48  4407.9 1339.35  4537.6 1335.31
  4598.6 1331.98  4690.2 1329.92  4710.6 1330.25  4726.7 1329.04  4888.7 1328.40
  4904.0 1326.53  4934.5 1324.67  4975.2 1325.81  4993.2 1323.21  5000.0 1323.62
  5004.8 1322.55  5005.1 1322.05  5009.0 1322.55  5014.1 1323.25  5028.3 1323.04
  5035.2 1324.69  5042.4 1322.90  5049.3 1326.08  5056.6 1325.54  5077.6 1327.22
  5099.0 1327.17  5120.1 1328.84  5247.1 1331.81  5473.9 1342.61  5572.8 1343.73
#Mann=3,-1,0
  4282.7    0.05       0  5004.8    0.05       0  5009.0    0.05       0
Bank Sta=5004.8,5009
Exp/Cntr=0.3,0.1

Type RM Length L Ch R = 1,4500,500,500,500
BEGIN DESCRIPTION:
HICKORY30 9.0
END DESCRIPTION:
XS GIS Cut Line= 3
      2771605.68     10185803.11      2771975.57     10186293.82
      2772755.68     10186503.11
#Sta/Elev= 30
  4385.5 1350.53  4392.8 1351.93  4407.4 1348.16  4457.3 1346.57  4528.1 1342.32
  4686.0 1338.11  4798.8 1333.64  4807.1 1334.14  4813.3 1333.03  4821.6 1333.78
  4827.9 1331.81  4836.2 1332.04  4842.5 1329.41  4857.0 1329.52  4863.3 1327.92
  4871.6 1327.55  4877.9 1328.71  4907.0 1327.93  4913.3 1328.91  4936.1 1327.94
  4971.5 1324.08  5014.0 1321.32  5014.3 1320.82  5018.2 1321.32  5072.6 1326.47
  5291.0 1326.52  5497.1 1335.27  5621.3 1337.77  5745.1 1342.38  5807.7 1343.39
#Mann=3,-1,0
  4385.5    0.05       0  5014.0    0.05       0  5018.2    0.05       0
Bank Sta=5014,5018.2
Exp/Cntr=0.3,0.1

Type RM Length L Ch R = 1,4000,500,500,500
BEGIN DESCRIPTION:
HICKORY30 8.0
END DESCRIPTION:
XS GIS Cut Line= 3
      2771655.72     10186653.12      2771982.91     10186694.52
      2772655.73     10186603.11
#Sta/Elev= 30
  4670.2 1332.80  4750.8 1329.24  4811.3 1325.80  4841.5 1324.66  4851.6 1324.89
  4873.0 1324.32  4891.9 1321.43  4902.0 1321.62  4942.3 1320.19  4948.1 1320.61
  4951.0 1320.02  4951.3 1319.52  4955.0 1319.52  4955.3 1320.02  5023.0 1320.69
  5053.3 1322.08  5083.5 1324.36  5164.3 1324.88  5234.9 1326.51  5270.3 1328.37
  5295.5 1329.01  5356.0 1332.49  5477.1 1336.46  5492.8 1337.52  5517.5 1338.16
  5565.2 1340.51  5598.2 1340.85  5608.3 1341.60  5658.8 1342.53  5679.0 1342.56
#Mann=3,-1,0
  4670.2    0.05       0  4951.0    0.03       0  4955.3    0.05       0
Bank Sta=4951,4955.3
Exp/Cntr=0.3,0.1

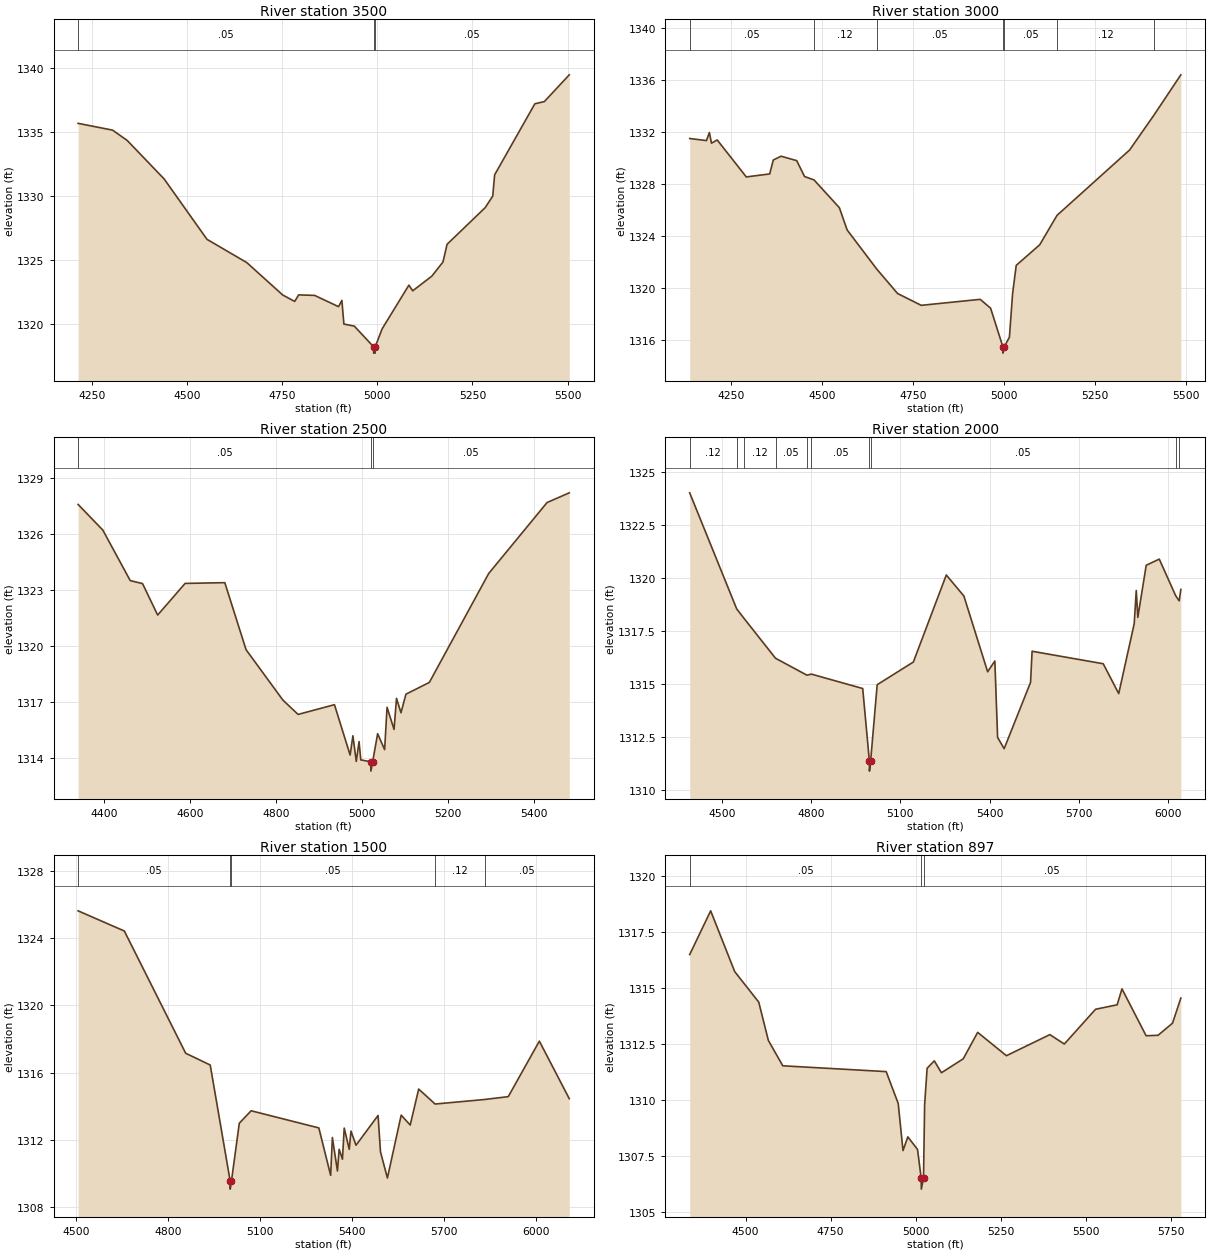
Type RM Length L Ch R = 1,3500,500,500,500
BEGIN DESCRIPTION:
HICKORY30 7.0
END DESCRIPTION:
XS GIS Cut Line= 3
      2771202.25     10186881.86      2771952.90     10187114.59
      2772455.72     10187153.11
#Sta/Elev= 30
  4214.1 1335.69  4304.7 1335.16  4343.3 1334.35  4440.3 1331.34  4552.7 1326.63
  4657.4 1324.81  4751.6 1322.28  4783.1 1321.78  4793.5 1322.29  4835.4 1322.25
  4898.2 1321.37  4907.0 1321.86  4912.3 1320.01  4939.6 1319.85  4990.2 1318.24
  4990.5 1317.74  4994.3 1317.74  4994.6 1318.24  5012.8 1319.64  5083.0 1323.05
  5093.1 1322.61  5143.2 1323.75  5172.6 1324.86  5183.3 1326.24  5283.6 1329.11
  5303.3 1330.01  5308.3 1331.67  5414.0 1337.22  5438.9 1337.39  5504.3 1339.48
#Mann=3,-1,0
  4214.1    0.05       0  4990.2    0.05       0  4994.6    0.05       0
Bank Sta=4990.2,4994.6
Exp/Cntr=0.3,0.1

Type RM Length L Ch R = 1,3000,500,500,500
BEGIN DESCRIPTION:
HICKORY30 6.0
END DESCRIPTION:
XS GIS Cut Line= 3
      2771125.82     10187159.61      2771871.98     10187596.78
      2772355.71     10187653.12
#Sta/Elev= 30
  4135.2 1331.50  4181.4 1331.34  4189.4 1331.96  4195.2 1331.14  4210.9 1331.39
  4291.0 1328.55  4355.4 1328.78  4365.3 1329.85  4386.8 1330.14  4429.8 1329.80
  4451.3 1328.58  4477.4 1328.32  4547.1 1326.19  4568.5 1324.48  4649.9 1321.48
  4707.3 1319.60  4772.5 1318.69  4934.8 1319.15  4963.4 1318.47  4997.0 1315.52
  4997.3 1315.02  5001.4 1315.52  5015.2 1316.25  5023.9 1319.59  5033.9 1321.76
  5098.6 1323.34  5146.2 1325.60  5346.0 1330.62  5413.1 1333.30  5487.0 1336.39
#Mann=7,-1,0
  4135.2    0.05       0  4477.4    0.12       0  4649.9    0.05       0
  4997.0    0.05       0  5001.4    0.05       0  5146.2    0.12       0
  5413.1    0.05       0
Bank Sta=4997,5001.4
Exp/Cntr=0.3,0.1

Type RM Length L Ch R = 1,2500,500,500,500
BEGIN DESCRIPTION:
HICKORY30 5.0
END DESCRIPTION:
XS GIS Cut Line= 3
      2771042.53     10187305.48      2771465.76     10187812.45
      2771890.86     10188040.06
#Sta/Elev= 30
  4339.6 1327.57  4397.1 1326.20  4460.9 1323.50  4489.5 1323.34  4524.7 1321.66
  4588.5 1323.35  4680.9 1323.39  4730.3 1319.81  4816.2 1317.11  4851.4 1316.35
  4936.0 1316.87  4972.4 1314.18  4978.9 1315.21  4986.7 1313.84  4993.2 1314.90
  4997.2 1313.92  5020.4 1313.82  5020.7 1313.32  5024.8 1313.82  5036.4 1315.32
  5052.7 1314.47  5058.3 1316.73  5074.6 1315.55  5080.3 1317.21  5090.7 1316.44
  5102.2 1317.43  5156.7 1318.06  5294.8 1323.88  5430.5 1327.67  5482.2 1328.19
#Mann=3,-1,0
  4339.6    0.05       0  5020.4    0.05       0  5024.8    0.05       0
Bank Sta=5020.4,5024.8
Exp/Cntr=0.3,0.1

Type RM Length L Ch R = 1,2000,500,500,500
BEGIN DESCRIPTION:
HICKORY30 4.0
END DESCRIPTION:
XS GIS Cut Line= 3
      2770959.18     10187437.39      2771159.89     10188011.94
      2771452.23     10189013.76
#Sta/Elev= 30
  4391.4 1324.01  4549.5 1318.53  4574.3 1318.08  4680.1 1316.20  4785.8 1315.40
  4800.9 1315.45  4973.4 1314.77  4995.7 1311.37  4996.1 1310.87  5000.2 1311.37
  5022.1 1314.95  5143.7 1316.02  5254.6 1320.13  5313.7 1319.14  5393.7 1315.56
  5417.9 1316.07  5427.2 1312.46  5449.2 1311.93  5538.0 1315.06  5543.2 1316.53
  5782.5 1315.94  5834.6 1314.53  5886.7 1317.83  5893.6 1319.40  5898.8 1318.13
  5927.1 1320.59  5971.0 1320.88  6026.3 1319.15  6038.0 1318.91  6043.6 1319.45
#Mann=10,-1,0
  4391.4    0.12       0  4549.5    0.05       0  4574.3    0.12       0
  4680.1    0.05       0  4785.8    0.12       0  4800.9    0.05       0
  4995.7    0.05       0  5000.2    0.05       0  6026.3    0.12       0
  6038.0    0.05       0
Bank Sta=4995.7,5000.2
Exp/Cntr=0.3,0.1

Type RM Length L Ch R = 1,1500,603,603,603
BEGIN DESCRIPTION:
HICKORY30 3.0
END DESCRIPTION:
XS GIS Cut Line= 3
      2770764.73     10187562.43      2770738.11     10188056.41
      2771249.88     10189039.71
#Sta/Elev= 30
  4505.3 1325.63  4656.2 1324.43  4856.5 1317.16  4936.6 1316.46  5001.5 1309.58
  5001.8 1309.08  5006.0 1309.58  5031.5 1313.00  5070.1 1313.74  5291.1 1312.72
  5329.7 1309.90  5335.3 1312.15  5351.8 1310.16  5357.4 1311.45  5368.2 1310.86
  5373.9 1312.71  5390.3 1311.45  5396.0 1312.53  5412.4 1311.69  5484.4 1313.46
  5492.3 1311.30  5514.9 1309.74  5559.9 1313.48  5589.3 1312.89  5617.0 1315.03
  5670.6 1314.14  5832.0 1314.41  5909.4 1314.58  6010.9 1317.88  6108.5 1314.46
#Mann=5,-1,0
  4505.3    0.05       0  5001.5    0.03       0  5006.0    0.05       0
  5670.6    0.12       0  5832.0    0.05       0
Bank Sta=5001.5,5006
Exp/Cntr=0.3,0.1

Type RM Length L Ch R = 1,897,397,397,397
BEGIN DESCRIPTION:
HICKORY30 2.0
END DESCRIPTION:
XS GIS Cut Line= 3
      2770195.27     10188076.28      2770663.00     10188548.00
      2771188.37     10189124.93
#Sta/Elev= 30
  4335.7 1316.49  4397.4 1318.44  4468.1 1315.73  4538.8 1314.37  4567.1 1312.66
  4609.5 1311.53  4913.6 1311.27  4949.0 1309.85  4963.1 1307.75  4977.3 1308.36
  5005.8 1307.80  5016.5 1306.53  5017.0 1306.03  5023.4 1306.53  5026.7 1309.80
  5034.0 1311.42  5055.1 1311.75  5076.1 1311.22  5140.2 1311.84  5182.7 1313.02
  5267.3 1311.98  5395.0 1312.92  5437.5 1312.50  5529.4 1314.05  5593.0 1314.25
  5607.1 1314.96  5678.1 1312.87  5713.2 1312.89  5755.8 1313.43  5780.3 1314.55
#Mann=3,-1,0
  4335.7    0.05       0  5016.5    0.05       0  5023.4    0.05       0
Bank Sta=5016.5,5023.4
Exp/Cntr=0.3,0.1

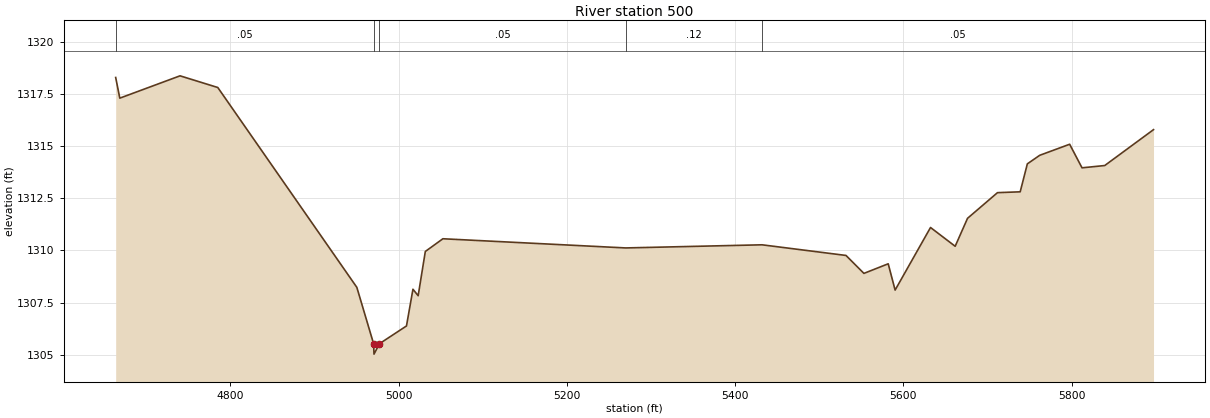
Type RM Length L Ch R = 1,500,0,0,0
BEGIN DESCRIPTION:
HICKORY30 1.0
END DESCRIPTION:
XS GIS Cut Line= 3
      2770125.84     10188277.67      2770299.71     10188565.53
      2770827.26     10189291.61
#Sta/Elev= 30
  4663.7 1318.29  4668.6 1317.30  4740.2 1318.37  4785.1 1317.81  4950.4 1308.23
  4970.3 1305.53  4970.8 1305.03  4977.3 1305.53  5009.4 1306.38  5017.1 1308.14
  5023.3 1307.83  5031.8 1309.95  5052.7 1310.56  5270.0 1310.12  5432.1 1310.27
  5531.9 1309.76  5553.2 1308.90  5582.1 1309.36  5590.3 1308.10  5632.4 1311.10
  5661.7 1310.20  5676.4 1311.54  5712.0 1312.77  5739.0 1312.81  5747.5 1314.15
  5762.2 1314.56  5797.8 1315.09  5812.5 1313.96  5839.5 1314.07  5897.5 1315.79
#Mann=5,-1,0
  4663.7    0.05       0  4970.3    0.05       0  4977.3    0.05       0
  5270.0    0.12       0  5432.1    0.05       0
Bank Sta=4970.3,4977.3
Exp/Cntr=0.3,0.1

Chan Stop Cuts=-1