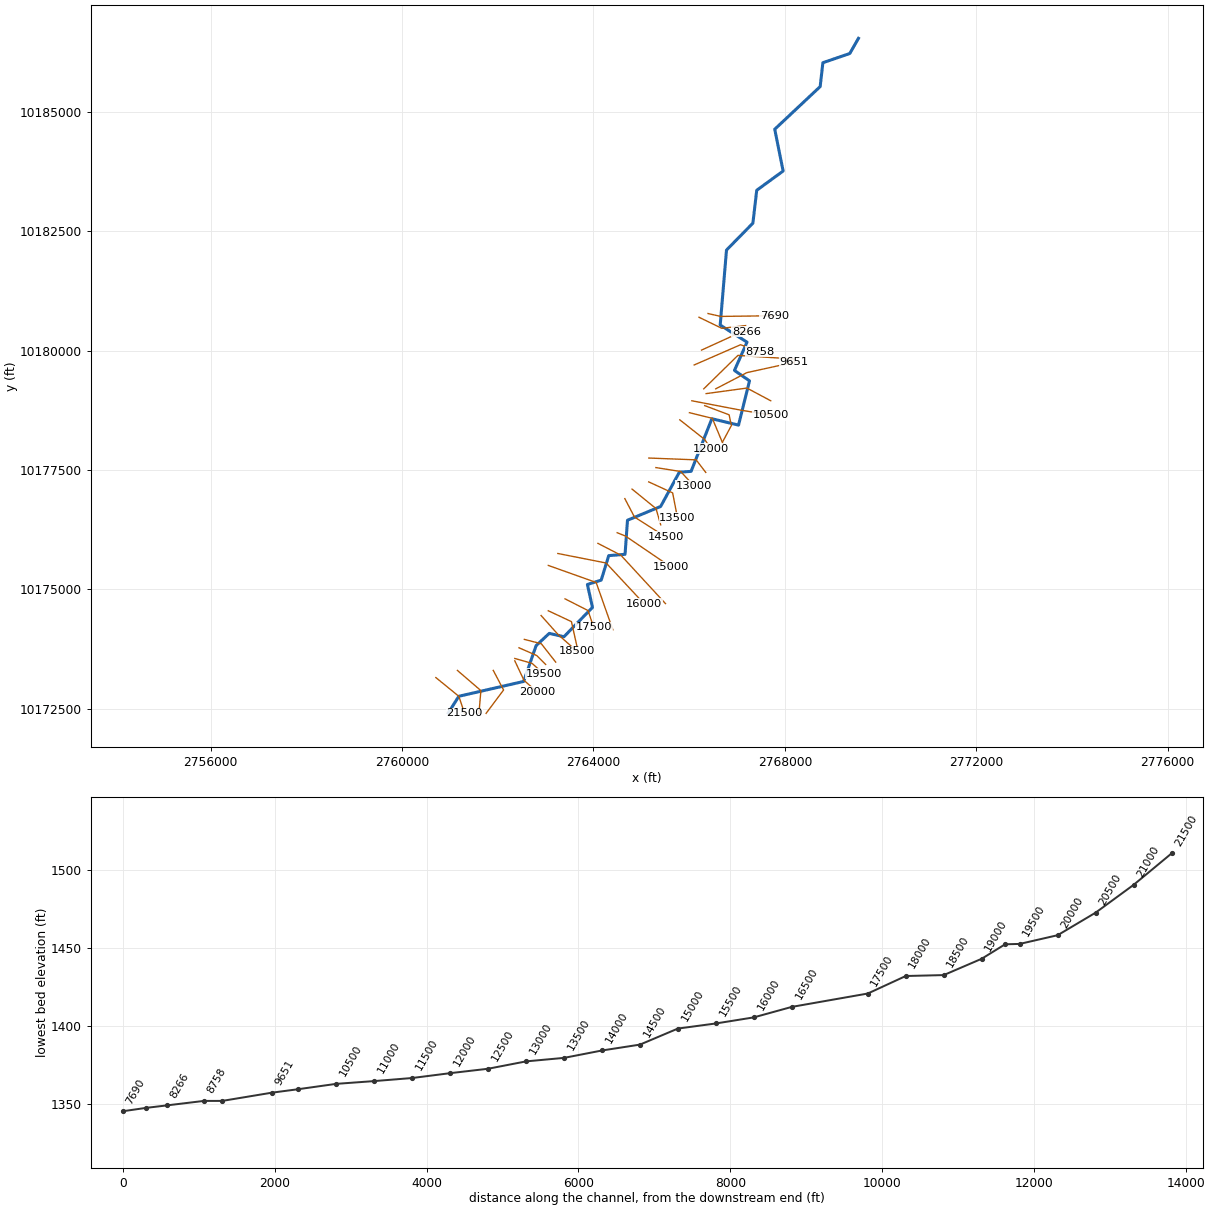
--- HICKORY31.prj (project) ---

Proj Title=HICKORY31 Base Level Engineering
Current Plan=p01
Default Exp/Contr=0.3,0.1
English Units
Geom File=g01
Flow File=f01
Plan File=p01
BEGIN DESCRIPTION:
HICKORY31
END DESCRIPTION:

--- HICKORY31.p01 (plan) ---

Plan Title=Multiple Run
Short Identifier=Multiple
Geom File=g01
Flow File=f01
Subcritical Flow
K Sum by GR= 0
Std Step Tol= 0.01
Critical Tol= 0.01
Num of Std Step Trials= 20
Max Error Tol= 0.3
Flow Tol Ratio= 0.001
Split Flow NTrial= 30
Split Flow Tol= 0.02
Split Flow Ratio= 0.02
Log Output Level= 0
Friction Slope Method= 1
Unsteady Friction Slope Method= 2
Unsteady Bridges Friction Slope Method= 1
Parabolic Critical Depth
Global Vel Dist=  1 , 1 , 1
Global Log Level= 0
CheckData=True
Encroach Param= -1, 0, 0, 0
BEGIN DESCRIPTION:
Multiple Run
END DESCRIPTION:

--- HICKORY31.f01 (steady flow) ---

Flow Title=Multiple
Number of Profiles=7
Profile Names=10-year,25-year,50-year,1pct_min,100-year,1pct_plu,500-year
River Rch & RM= HICKORY31,Reach-1,21500
     419     674    1392    1138    1951    3346    2830
River Rch & RM= HICKORY31,Reach-1,14000
     772    1301    2387    1761    3368    6441    4807
River Rch & RM= HICKORY31,Reach-1,6000
    1061    1829    3182    2249    4509    9038    6385
Boundary for River Rch & Prof#=HICKORY31,Reach-1,1
Up Type=0
Dn Type=3
Dn Slope=0.005
Boundary for River Rch & Prof#=HICKORY31,Reach-1,2
Up Type=0
Dn Type=3
Dn Slope=0.005
Boundary for River Rch & Prof#=HICKORY31,Reach-1,3
Up Type=0
Dn Type=3
Dn Slope=0.005
Boundary for River Rch & Prof#=HICKORY31,Reach-1,4
Up Type=0
Dn Type=3
Dn Slope=0.005
Boundary for River Rch & Prof#=HICKORY31,Reach-1,5
Up Type=0
Dn Type=3
Dn Slope=0.005
Boundary for River Rch & Prof#=HICKORY31,Reach-1,6
Up Type=0
Dn Type=3
Dn Slope=0.005
Boundary for River Rch & Prof#=HICKORY31,Reach-1,7
Up Type=0
Dn Type=3
Dn Slope=0.005

--- HICKORY31.g01 (geometry) ---

Geom Title=Existing Conditions

River Reach=HICKORY31,Reach-1
Reach XY= 30
      2760964.50     10172410.00      2761185.00     10172761.00
      2762540.25     10173072.00      2762801.00     10173822.00
      2763075.75     10174079.00      2763383.00     10174009.00
      2763979.50     10174624.00      2763873.00     10175104.00
      2764161.75     10175195.00      2764319.25     10175708.00
      2764660.50     10175736.00      2764711.50     10176450.00
      2765404.25     10176738.00      2765794.50     10177456.00
      2766040.75     10177474.00      2766475.00     10178577.00
      2767032.50     10178443.00      2767261.75     10179370.00
      2766947.00     10179589.00      2767209.75     10180181.00
      2766649.25     10180539.00      2766780.50     10182110.00
      2767332.50     10182674.00      2767412.75     10183363.00
      2767964.75     10183767.00      2767789.00     10184642.00
      2768739.00     10185536.00      2768795.25     10186036.00
      2769357.75     10186229.00      2769539.25     10186547.00

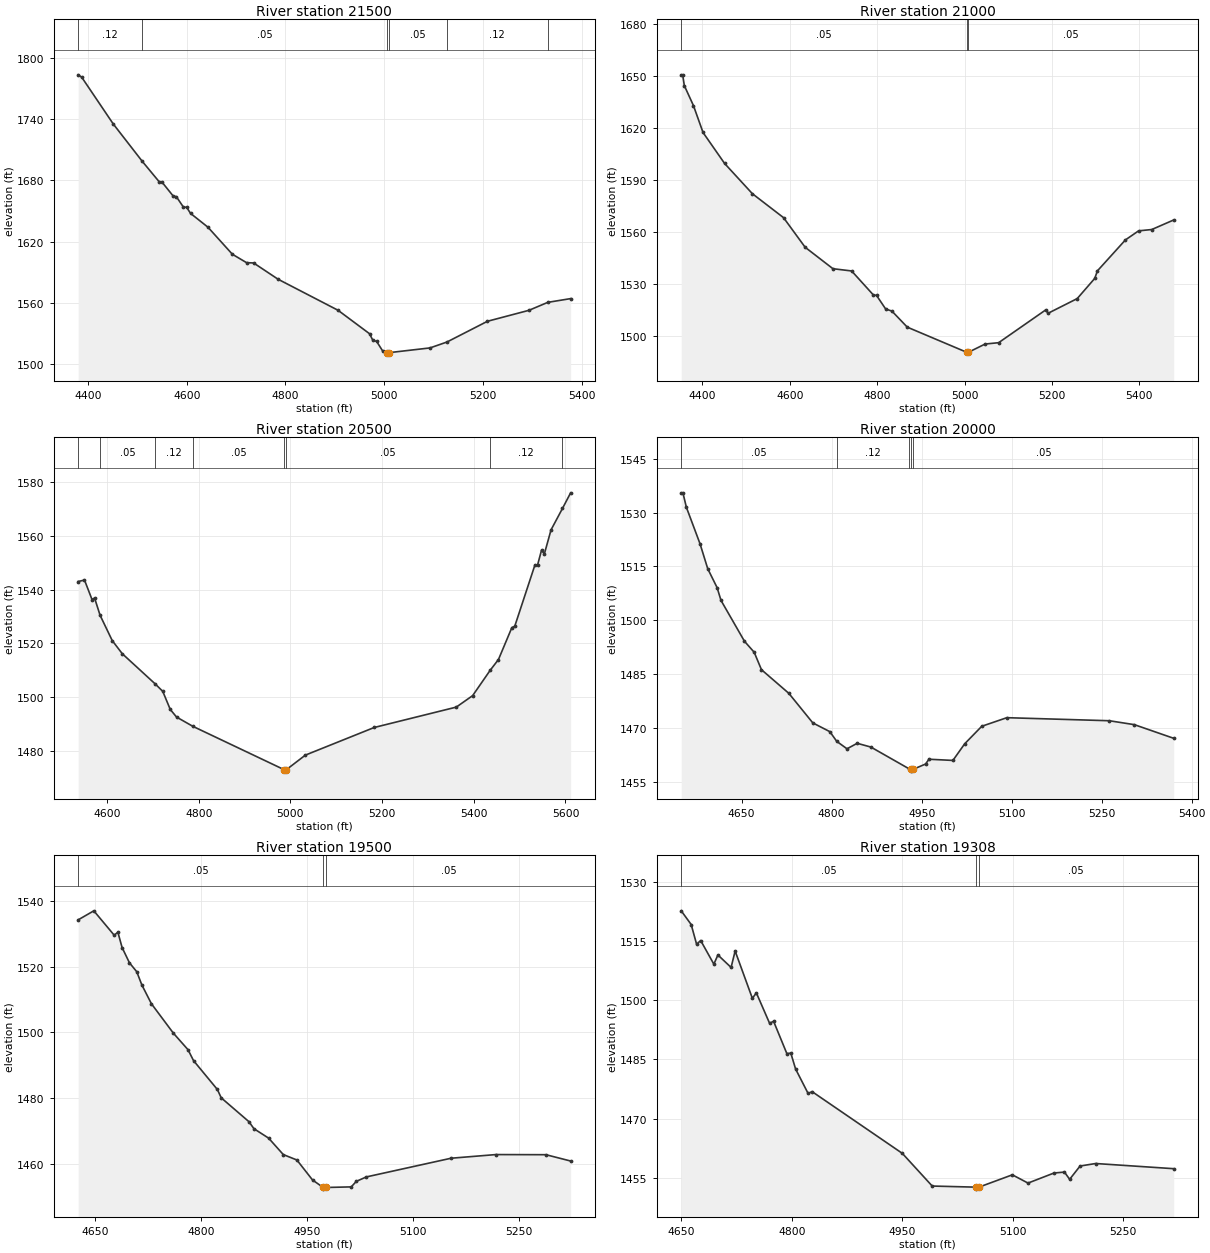
Type RM Length L Ch R = 1,21500,500,500,500
BEGIN DESCRIPTION:
HICKORY31 42.0
END DESCRIPTION:
XS GIS Cut Line= 3
      2760705.69     10173153.10      2761185.87     10172761.04
      2761305.70     10172403.07
#Sta/Elev= 30
  4380.1 1783.83  4387.3 1781.48  4451.2 1735.52  4510.1 1698.72  4543.8 1678.98
  4550.2 1678.22  4572.5 1664.76  4579.0 1664.05  4593.3 1653.82  4599.8 1653.67
  4607.7 1647.69  4642.9 1634.13  4692.4 1607.53  4721.1 1599.28  4735.5 1598.95
  4785.0 1582.98  4906.4 1552.49  4970.3 1529.40  4976.7 1523.14  4984.6 1521.85
  4996.7 1512.56  5006.4 1510.87  5006.6 1510.37  5010.4 1510.87  5092.7 1515.49
  5126.9 1521.26  5209.1 1541.68  5293.1 1552.44  5331.3 1560.27  5377.5 1563.94
#Mann=6,-1,0
  4380.1    0.12       0  4510.1    0.05       0  5006.4    0.05       0
  5010.4    0.05       0  5126.9    0.12       0  5331.3    0.05       0
Bank Sta=5006.4,5010.4
Exp/Cntr=0.3,0.1

Type RM Length L Ch R = 1,21000,500,500,500
BEGIN DESCRIPTION:
HICKORY31 41.0
END DESCRIPTION:
XS GIS Cut Line= 3
      2761155.71     10173303.09      2761647.06     10172880.01
      2761605.68     10172403.10
#Sta/Elev= 30
  4351.6 1650.85  4354.9 1650.85  4358.7 1644.62  4379.6 1633.08  4401.5 1617.57
  4450.9 1599.69  4514.5 1582.23  4585.8 1568.41  4635.2 1551.34  4698.8 1538.96
  4741.6 1537.66  4791.0 1523.90  4798.7 1523.51  4819.5 1515.70  4833.8 1514.50
  4868.9 1505.24  5004.9 1490.74  5005.2 1490.24  5008.9 1490.74  5047.1 1495.49
  5078.0 1496.26  5186.0 1515.22  5191.0 1513.21  5257.9 1521.72  5298.0 1533.36
  5304.1 1537.71  5368.3 1555.60  5398.4 1560.81  5428.5 1561.57  5478.7 1567.09
#Mann=3,-1,0
  4351.6    0.05       0  5004.9    0.05       0  5008.9    0.05       0
Bank Sta=5004.9,5008.9
Exp/Cntr=0.3,0.1

Type RM Length L Ch R = 1,20500,500,500,500
BEGIN DESCRIPTION:
HICKORY31 40.0
END DESCRIPTION:
XS GIS Cut Line= 3
      2761905.71     10173303.07      2762121.02     10172893.29
      2761755.71     10172403.15
#Sta/Elev= 30
  4537.1 1543.03  4550.9 1543.57  4567.3 1536.33  4572.9 1536.89  4584.9 1530.47
  4611.4 1521.04  4633.4 1516.14  4705.0 1504.93  4721.6 1502.15  4738.0 1495.41
  4751.7 1492.58  4787.1 1489.14  4986.9 1472.95  4987.2 1472.45  4990.9 1472.95
  5032.7 1478.41  5182.8 1488.69  5361.9 1496.28  5397.6 1500.56  5435.7 1509.96
  5453.9 1514.00  5483.1 1525.87  5489.4 1526.37  5533.2 1549.07  5539.4 1549.32
  5547.8 1554.68  5554.0 1553.31  5568.6 1562.27  5593.5 1570.23  5611.3 1576.04
#Mann=8,-1,0
  4537.1    0.12       0  4584.9    0.05       0  4705.0    0.12       0
  4787.1    0.05       0  4986.9    0.05       0  4990.9    0.05       0
  5435.7    0.12       0  5593.5    0.05       0
Bank Sta=4986.9,4990.9
Exp/Cntr=0.3,0.1

Type RM Length L Ch R = 1,20000,500,500,500
BEGIN DESCRIPTION:
HICKORY31 39.0
END DESCRIPTION:
XS GIS Cut Line= 3
      2762355.68     10173503.11      2762547.52     10173095.28
      2762825.51     10172850.95
#Sta/Elev= 30
  4549.3 1535.51  4552.1 1535.51  4557.9 1531.48  4580.7 1521.29  4593.5 1514.37
  4609.1 1509.11  4615.6 1505.55  4654.7 1494.18  4670.9 1491.12  4683.0 1486.27
  4728.6 1479.69  4768.6 1471.45  4797.0 1469.01  4808.5 1466.31  4825.6 1464.24
  4842.6 1465.77  4865.4 1464.72  4928.7 1458.70  4931.8 1458.52  4932.0 1458.02
  4935.8 1458.52  4956.6 1460.00  4962.1 1461.33  5002.1 1461.00  5021.8 1465.64
  5050.2 1470.51  5092.0 1472.90  5262.8 1472.05  5304.5 1470.96  5370.1 1467.16
#Mann=5,-1,0
  4549.3    0.05       0  4808.5    0.12       0  4928.7    0.05       0
  4931.8    0.05       0  4935.8    0.05       0
Bank Sta=4931.8,4935.8
Exp/Cntr=0.3,0.1

Type RM Length L Ch R = 1,19500,192,192,192
BEGIN DESCRIPTION:
HICKORY31 38.0
END DESCRIPTION:
XS GIS Cut Line= 3
      2762355.68     10173553.11      2762716.20     10173451.73
      2762956.56     10173234.62
#Sta/Elev= 30
  4625.5 1534.18  4647.7 1536.92  4676.6 1529.52  4681.8 1530.43  4687.8 1525.78
  4698.2 1521.15  4708.6 1518.43  4715.8 1514.43  4729.4 1508.71  4760.5 1499.79
  4781.3 1494.76  4789.1 1491.45  4822.9 1482.69  4828.4 1480.15  4867.6 1472.93
  4874.8 1470.78  4895.6 1467.92  4916.4 1462.93  4935.7 1461.28  4957.9 1455.21
  4973.0 1452.94  4973.2 1452.44  4977.0 1452.94  5012.8 1453.12  5019.9 1454.79
  5034.1 1456.14  5154.4 1461.82  5218.0 1462.93  5288.9 1462.89  5323.9 1460.97
#Mann=3,-1,0
  4625.5    0.05       0  4973.0    0.05       0  4977.0    0.05       0
Bank Sta=4973,4977
Exp/Cntr=0.3,0.1

Type RM Length L Ch R = 1,19308,308,308,308
BEGIN DESCRIPTION:
Mapping XS a357de8b
END DESCRIPTION:
XS GIS Cut Line= 3
      2762443.33     10173777.26      2762813.12     10173615.80
      2763000.64     10173428.28
#Sta/Elev= 30
  4649.9 1522.61  4663.4 1519.15  4670.8 1514.14  4676.3 1515.10  4694.2 1509.12
  4699.7 1511.44  4717.6 1508.29  4723.1 1512.44  4746.5 1500.47  4751.9 1501.86
  4769.9 1494.15  4775.3 1494.67  4793.3 1486.50  4798.7 1486.60  4805.2 1482.59
  4822.2 1476.40  4827.6 1476.87  4950.1 1461.25  4990.7 1452.98  5050.1 1452.70
  5050.3 1452.20  5054.1 1452.70  5099.5 1455.82  5120.8 1453.73  5156.1 1456.28
  5170.3 1456.51  5177.3 1454.68  5191.5 1458.05  5212.7 1458.68  5318.6 1457.37
#Mann=3,-1,0
  4649.9    0.05       0  5050.1    0.05       0  5054.1    0.05       0
Bank Sta=5050.1,5054.1
Exp/Cntr=0.3,0.1

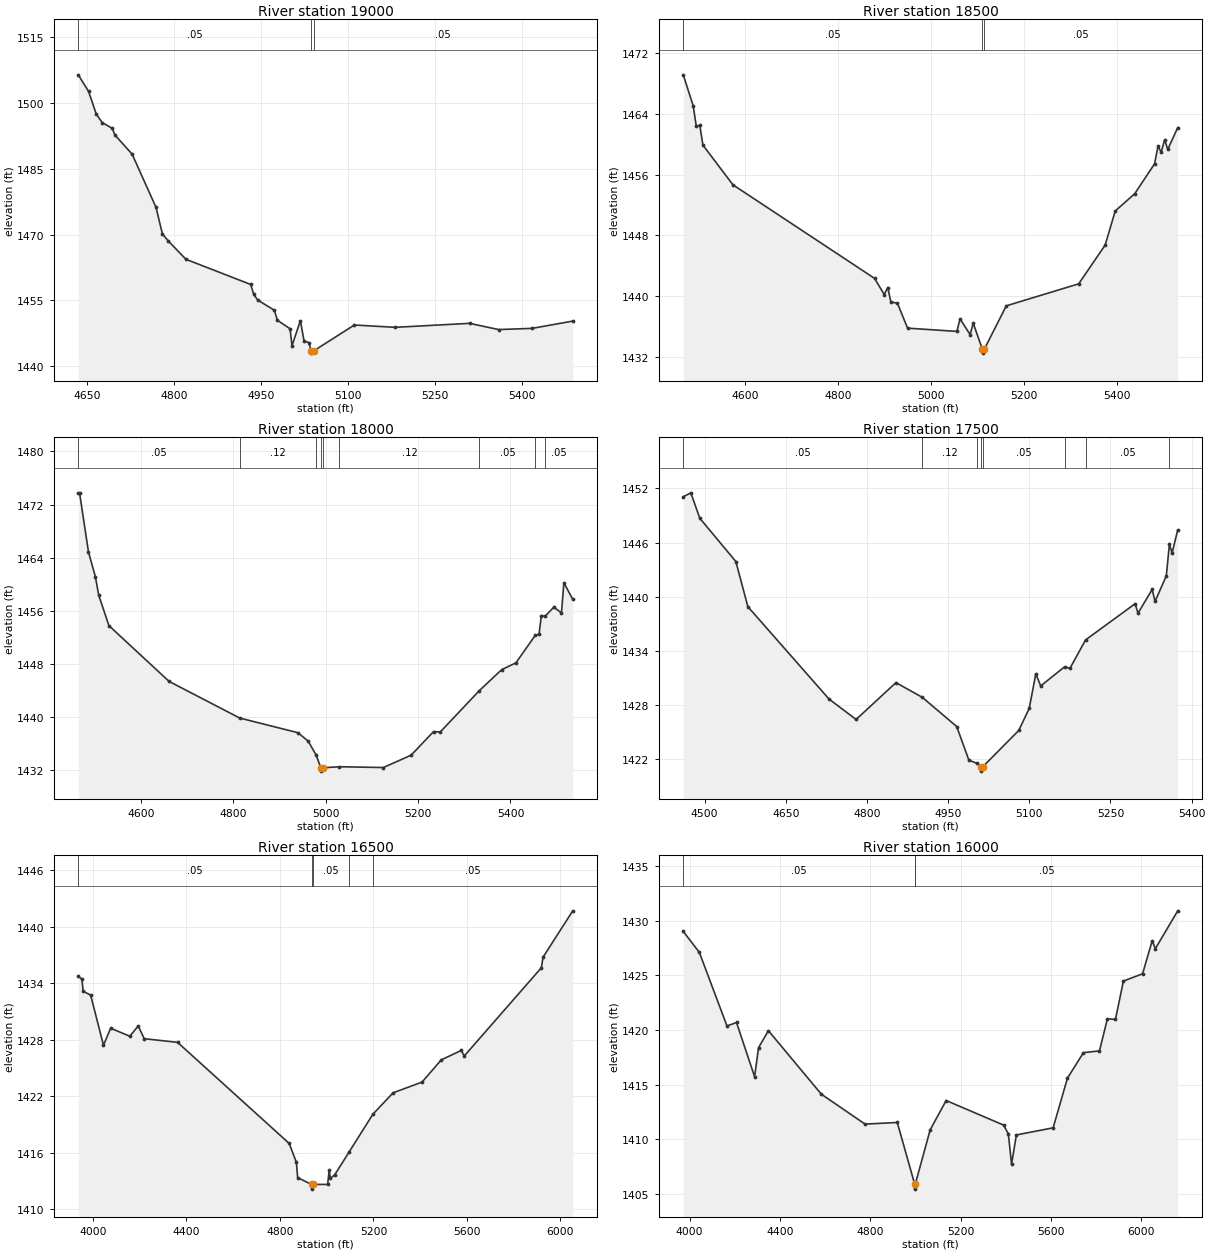
Type RM Length L Ch R = 1,19000,500,500,500
BEGIN DESCRIPTION:
HICKORY31 37.0
END DESCRIPTION:
XS GIS Cut Line= 3
      2762555.70     10173953.11      2762909.58     10173862.06
      2763210.22     10173477.92
#Sta/Elev= 30
  4634.6 1506.47  4652.4 1502.67  4665.6 1497.52  4675.9 1495.58  4693.1 1494.26
  4698.2 1492.67  4727.5 1488.37  4768.8 1476.19  4779.7 1470.18  4789.5 1468.60
  4820.4 1464.36  4932.2 1458.61  4937.4 1456.34  4944.3 1455.05  4972.9 1452.73
  4978.1 1450.45  5000.0 1448.50  5003.4 1444.65  5017.9 1450.34  5024.2 1445.71
  5032.3 1445.36  5036.7 1443.44  5036.9 1442.94  5040.7 1443.44  5111.0 1449.36
  5181.5 1448.83  5309.9 1449.74  5359.7 1448.32  5417.5 1448.59  5487.8 1450.25
#Mann=3,-1,0
  4634.6    0.05       0  5036.7    0.03       0  5040.7    0.05       0
Bank Sta=5036.7,5040.7
Exp/Cntr=0.3,0.1

Type RM Length L Ch R = 1,18500,500,500,500
BEGIN DESCRIPTION:
HICKORY31 36.0
END DESCRIPTION:
XS GIS Cut Line= 3
      2762905.66     10174453.14      2763259.63     10174055.85
      2763655.71     10173703.08
#Sta/Elev= 30
  4467.9 1469.15  4489.3 1465.06  4495.9 1462.38  4503.5 1462.49  4510.2 1459.89
  4574.5 1454.67  4878.9 1442.34  4899.8 1440.21  4907.3 1441.13  4914.0 1439.24
  4928.2 1439.06  4949.9 1435.78  5055.9 1435.35  5062.6 1437.01  5084.3 1434.93
  5091.0 1436.43  5110.7 1432.99  5111.0 1432.49  5114.7 1432.99  5162.0 1438.72
  5317.6 1441.62  5374.4 1446.72  5396.2 1451.22  5438.0 1453.49  5480.6 1457.43
  5488.1 1459.77  5494.8 1458.96  5502.3 1460.59  5509.0 1459.33  5530.4 1462.20
#Mann=3,-1,0
  4467.9    0.05       0  5110.7    0.05       0  5114.7    0.05       0
Bank Sta=5110.7,5114.7
Exp/Cntr=0.3,0.1

Type RM Length L Ch R = 1,18000,500,500,500
BEGIN DESCRIPTION:
HICKORY31 35.0
END DESCRIPTION:
XS GIS Cut Line= 3
      2763055.66     10174553.12      2763539.78     10174325.18
      2763655.69     10173803.09
#Sta/Elev= 30
  4464.9 1473.77  4467.7 1473.77  4487.0 1464.87  4501.9 1461.16  4509.1 1458.39
  4531.2 1453.79  4661.4 1445.40  4814.1 1439.89  4940.2 1437.68  4962.3 1436.42
  4980.0 1434.27  4989.5 1432.40  4989.8 1431.90  4993.5 1432.40  5030.0 1432.56
  5125.0 1432.44  5185.1 1434.30  5233.7 1437.85  5248.0 1437.78  5332.8 1444.02
  5381.1 1447.17  5411.9 1448.19  5454.2 1452.38  5461.8 1452.46  5466.9 1455.31
  5474.8 1455.19  5493.8 1456.56  5510.4 1455.71  5515.6 1460.24  5534.8 1457.75
#Mann=9,-1,0
  4464.9    0.05       0  4814.1    0.12       0  4980.0    0.05       0
  4989.5    0.03       0  4993.5    0.05       0  5030.0    0.12       0
  5332.8    0.05       0  5454.2    0.12       0  5474.8    0.05       0
Bank Sta=4989.5,4993.5
Exp/Cntr=0.3,0.1

Type RM Length L Ch R = 1,17500,1000,1000,1000
BEGIN DESCRIPTION:
HICKORY31 34.0
END DESCRIPTION:
XS GIS Cut Line= 3
      2763405.65     10174803.13      2763886.02     10174557.78
      2764005.68     10174203.12
#Sta/Elev= 30
  4460.6 1451.07  4474.6 1451.51  4491.2 1448.69  4557.8 1443.90  4580.0 1438.90
  4730.0 1428.67  4780.0 1426.41  4853.6 1430.49  4902.1 1428.87  4965.9 1425.63
  4988.4 1421.90  5002.6 1421.57  5010.4 1421.19  5010.6 1420.69  5014.4 1421.19
  5080.6 1425.20  5099.9 1427.64  5112.1 1431.48  5121.0 1430.12  5165.6 1432.26
  5175.0 1432.06  5204.0 1435.22  5295.6 1439.23  5300.9 1438.18  5327.1 1440.81
  5332.4 1439.48  5353.2 1442.32  5358.9 1445.81  5363.9 1444.85  5374.3 1447.41
#Mann=8,-1,0
  4460.6    0.05       0  4902.1    0.12       0  5002.6    0.05       0
  5010.4    0.07       0  5014.4    0.05       0  5165.6    0.12       0
  5204.0    0.05       0  5358.9    0.12       0
Bank Sta=5010.4,5014.4
Exp/Cntr=0.3,0.1

Type RM Length L Ch R = 1,16500,500,500,500
BEGIN DESCRIPTION:
HICKORY31 33.0
END DESCRIPTION:
XS GIS Cut Line= 3
      2763055.70     10175503.11      2764056.39     10175146.00
      2764405.67     10174153.15
#Sta/Elev= 30
  3937.5 1434.75  3952.9 1434.45  3958.7 1433.16  3990.6 1432.74  4045.3 1427.42
  4076.1 1429.23  4157.9 1428.38  4194.0 1429.47  4219.5 1428.12  4362.2 1427.73
  4839.8 1416.99  4870.6 1414.97  4875.9 1413.36  4935.5 1412.64  4935.8 1412.14
  4939.5 1412.64  5004.2 1412.64  5010.7 1414.12  5016.0 1413.28  5034.9 1413.68
  5095.1 1416.05  5197.5 1420.09  5284.1 1422.37  5407.9 1423.51  5490.2 1425.87
  5575.5 1426.87  5588.4 1426.28  5918.5 1435.66  5925.3 1436.77  6052.5 1441.70
#Mann=5,-1,0
  3937.5    0.05       0  4935.5    0.05       0  4939.5    0.05       0
  5095.1    0.12       0  5197.5    0.05       0
Bank Sta=4935.5,4939.5
Exp/Cntr=0.3,0.1

Type RM Length L Ch R = 1,16000,500,500,500
BEGIN DESCRIPTION:
HICKORY31 32.0
END DESCRIPTION:
XS GIS Cut Line= 3
      2763255.66     10175753.12      2764264.58     10175553.89
      2765055.71     10174703.08
#Sta/Elev= 30
  3971.6 1429.02  4043.0 1427.09  4165.3 1420.36  4207.5 1420.68  4287.6 1415.72
  4305.0 1418.37  4348.8 1419.93  4583.2 1414.12  4776.9 1411.38  4919.6 1411.53
  4996.0 1405.93  4996.3 1405.43  5000.0 1405.93  5065.1 1410.85  5136.0 1413.54
  5390.5 1411.29  5411.5 1410.49  5425.7 1407.72  5447.2 1410.39  5609.9 1411.04
  5673.4 1415.59  5744.2 1417.92  5815.1 1418.08  5850.3 1421.02  5886.0 1420.96
  5921.1 1424.47  6006.1 1425.14  6048.7 1428.16  6062.8 1427.44  6161.8 1430.90
#Mann=3,-1,0
  3971.6    0.05       0  4996.0    0.05       0  5000.0    0.05       0
Bank Sta=4996,5000
Exp/Cntr=0.3,0.1

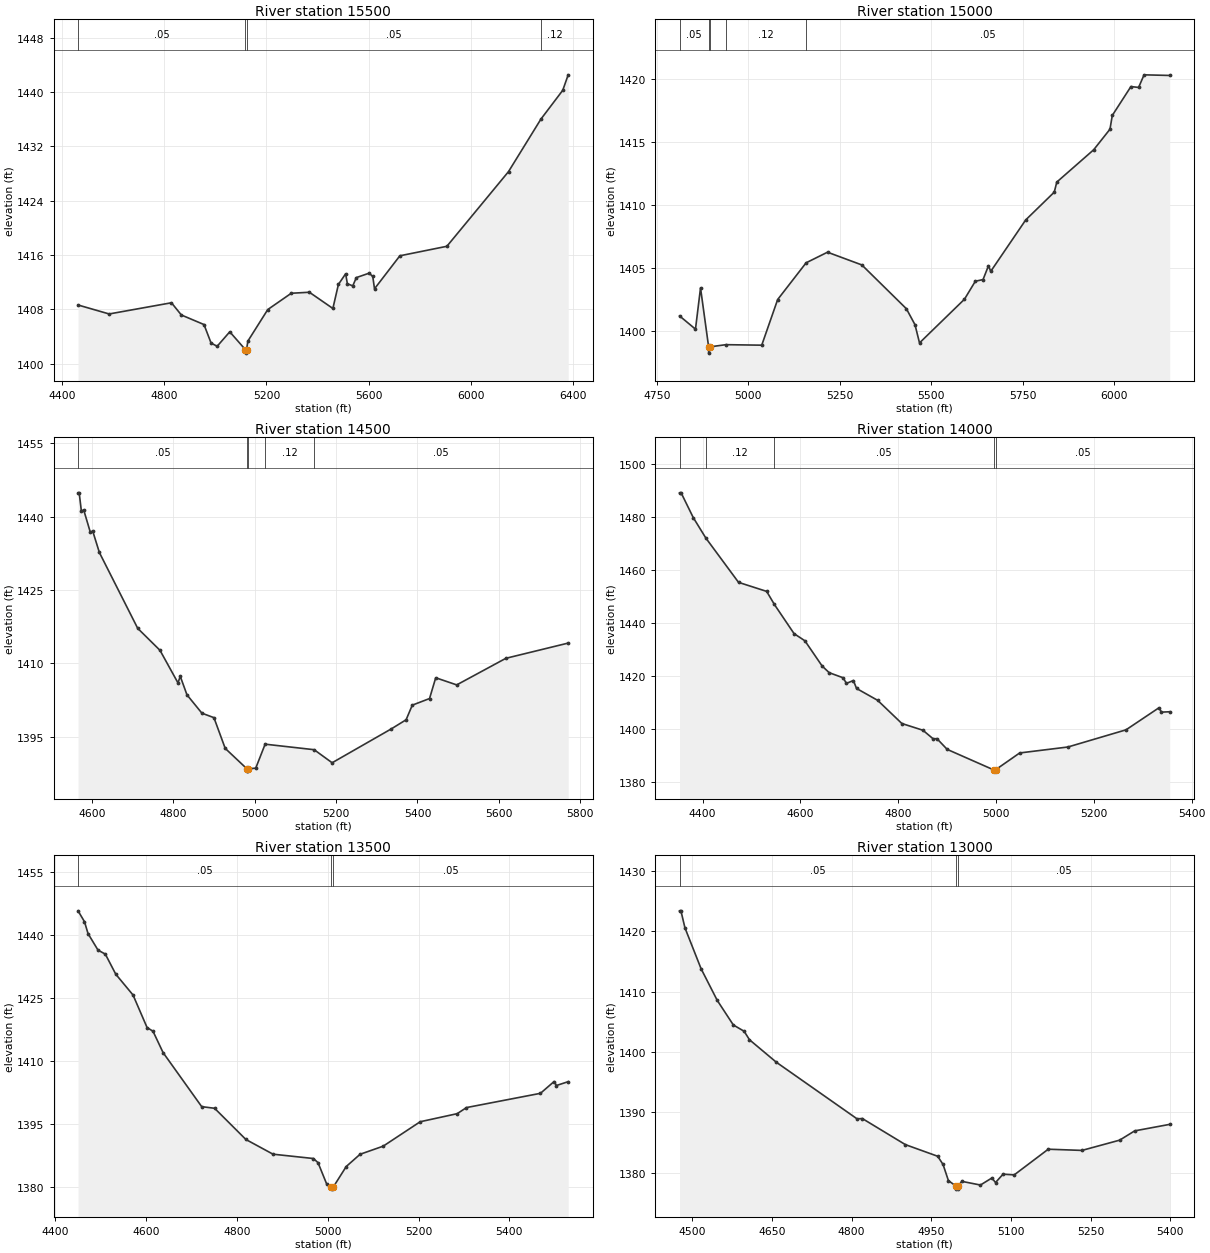
Type RM Length L Ch R = 1,15500,500,500,500
BEGIN DESCRIPTION:
HICKORY31 31.0
END DESCRIPTION:
XS GIS Cut Line= 3
      2764094.34     10175964.78      2764571.28     10175718.45
      2765505.71     10174703.08
#Sta/Elev= 30
  4463.2 1408.62  4584.8 1407.30  4828.5 1408.95  4867.1 1407.15  4955.7 1405.74
  4983.5 1403.01  5007.2 1402.54  5056.5 1404.67  5118.0 1402.03  5118.3 1401.53
  5122.0 1402.03  5127.4 1403.31  5205.1 1407.95  5297.0 1410.35  5367.8 1410.50
  5459.7 1408.11  5481.3 1411.65  5509.6 1413.22  5516.4 1411.75  5537.4 1411.44
  5551.6 1412.66  5601.5 1413.31  5615.7 1412.82  5622.5 1411.01  5721.7 1415.87
  5905.5 1417.27  6146.5 1428.27  6273.1 1436.00  6358.6 1440.25  6379.9 1442.53
#Mann=4,-1,0
  4463.2    0.05       0  5118.0    0.03       0  5122.0    0.05       0
  6273.1    0.12       0
Bank Sta=5118,5122
Exp/Cntr=0.3,0.1

Type RM Length L Ch R = 1,15000,500,500,500
BEGIN DESCRIPTION:
HICKORY31 30.0
END DESCRIPTION:
XS GIS Cut Line= 3
      2764495.39     10176188.73      2764669.26     10176118.29
      2765620.42     10175469.96
#Sta/Elev= 30
  4812.4 1401.22  4855.9 1400.17  4869.7 1403.44  4891.8 1398.77  4892.0 1398.27
  4895.8 1398.77  4939.1 1398.94  5036.9 1398.90  5080.4 1402.52  5158.1 1405.43
  5216.5 1406.27  5310.3 1405.26  5431.9 1401.79  5455.5 1400.52  5467.8 1399.08
  5590.5 1402.54  5620.3 1403.97  5641.3 1404.10  5656.2 1405.20  5662.3 1404.75
  5757.9 1408.83  5835.8 1411.03  5842.8 1411.83  5943.5 1414.39  5988.0 1416.02
  5994.3 1417.11  6045.2 1419.40  6066.2 1419.33  6081.1 1420.33  6151.1 1420.28
#Mann=5,-1,0
  4812.4    0.05       0  4891.8    0.07       0  4895.8    0.05       0
  4939.1    0.12       0  5158.1    0.05       0
Bank Sta=4891.8,4895.8
Exp/Cntr=0.3,0.1

Type RM Length L Ch R = 1,14500,500,500,500
BEGIN DESCRIPTION:
HICKORY31 29.0
END DESCRIPTION:
XS GIS Cut Line= 3
      2764655.71     10176903.07      2764856.39     10176518.03
      2765505.65     10176103.13
#Sta/Elev= 30
  4565.8 1444.89  4568.6 1444.89  4574.0 1441.13  4579.6 1441.42  4596.1 1436.79
  4601.7 1437.11  4618.2 1432.69  4712.4 1417.19  4767.2 1412.69  4811.4 1406.03
  4817.0 1407.38  4833.5 1403.59  4870.2 1399.84  4899.8 1398.92  4927.5 1392.64
  4980.5 1388.49  4980.8 1387.99  4984.5 1388.49  5002.5 1388.59  5025.6 1393.50
  5146.1 1392.37  5190.3 1389.70  5335.8 1396.63  5372.1 1398.49  5387.3 1401.48
  5429.7 1402.83  5444.9 1407.08  5496.5 1405.62  5617.4 1411.06  5770.5 1414.17
#Mann=5,-1,0
  4565.8    0.05       0  4980.5    0.05       0  4984.5    0.05       0
  5025.6    0.12       0  5146.1    0.05       0
Bank Sta=4980.5,4984.5
Exp/Cntr=0.3,0.1

Type RM Length L Ch R = 1,14000,500,500,500
BEGIN DESCRIPTION:
HICKORY31 28.0
END DESCRIPTION:
XS GIS Cut Line= 3
      2764805.70     10177103.10      2765307.19     10176694.30
      2765405.68     10176353.13
#Sta/Elev= 30
  4353.0 1489.30  4356.2 1489.30  4381.0 1479.96  4406.7 1472.24  4473.6 1455.50
  4531.1 1452.09  4546.9 1447.15  4587.1 1436.15  4609.3 1433.43  4644.5 1423.92
  4658.9 1421.40  4687.6 1419.46  4694.1 1417.35  4708.4 1418.44  4714.9 1415.44
  4758.0 1410.96  4807.5 1402.21  4850.6 1399.66  4871.4 1396.44  4879.3 1396.48
  4900.2 1392.44  4994.9 1384.73  4995.2 1384.23  4999.0 1384.73  5048.4 1391.09
  5147.0 1393.34  5265.8 1399.82  5333.1 1408.14  5338.3 1406.50  5355.1 1406.65
#Mann=5,-1,0
  4353.0    0.05       0  4406.7    0.12       0  4546.9    0.05       0
  4994.9    0.05       0  4999.0    0.05       0
Bank Sta=4994.9,4999
Exp/Cntr=0.3,0.1

Type RM Length L Ch R = 1,13500,500,500,500
BEGIN DESCRIPTION:
HICKORY31 27.0
END DESCRIPTION:
XS GIS Cut Line= 3
      2765155.70     10177253.10      2765655.22     10177022.93
      2765755.68     10176503.15
#Sta/Elev= 30
  4450.0 1445.70  4464.2 1443.11  4472.0 1440.28  4494.0 1436.35  4510.1 1435.40
  4533.1 1430.62  4571.1 1425.67  4602.0 1417.94  4615.1 1417.05  4637.2 1411.99
  4722.3 1399.12  4750.7 1398.73  4819.6 1391.31  4879.4 1387.81  4968.4 1386.78
  4978.5 1385.79  4997.5 1380.73  5007.9 1380.00  5008.2 1379.50  5012.1 1380.00
  5040.6 1384.88  5071.1 1387.79  5122.0 1389.72  5203.5 1395.53  5285.0 1397.45
  5305.4 1398.90  5468.3 1402.29  5498.4 1405.10  5503.5 1404.15  5529.4 1405.06
#Mann=3,-1,0
  4450.0    0.05       0  5007.9    0.05       0  5012.1    0.05       0
Bank Sta=5007.9,5012.1
Exp/Cntr=0.3,0.1

Type RM Length L Ch R = 1,13000,500,500,500
BEGIN DESCRIPTION:
HICKORY31 26.0
END DESCRIPTION:
XS GIS Cut Line= 3
      2765305.64     10177553.12      2765823.06     10177470.98
      2766092.67     10177176.72
#Sta/Elev= 30
  4476.1 1423.40  4478.7 1423.40  4486.3 1420.57  4516.6 1413.81  4547.0 1408.56
  4577.4 1404.47  4597.7 1403.43  4607.8 1402.02  4658.4 1398.29  4810.3 1388.91
  4820.4 1388.95  4901.4 1384.63  4962.2 1382.70  4972.3 1381.34  4982.4 1378.66
  4996.7 1377.75  4997.0 1377.25  5000.6 1377.25  5000.9 1377.75  5007.6 1378.54
  5042.7 1377.93  5064.3 1379.10  5071.1 1378.34  5085.3 1379.73  5106.3 1379.61
  5170.4 1383.87  5233.9 1383.67  5304.8 1385.37  5333.2 1386.91  5399.1 1387.99
#Mann=3,-1,0
  4476.1    0.05       0  4996.7    0.05       0  5000.9    0.05       0
Bank Sta=4996.7,5000.9
Exp/Cntr=0.3,0.1

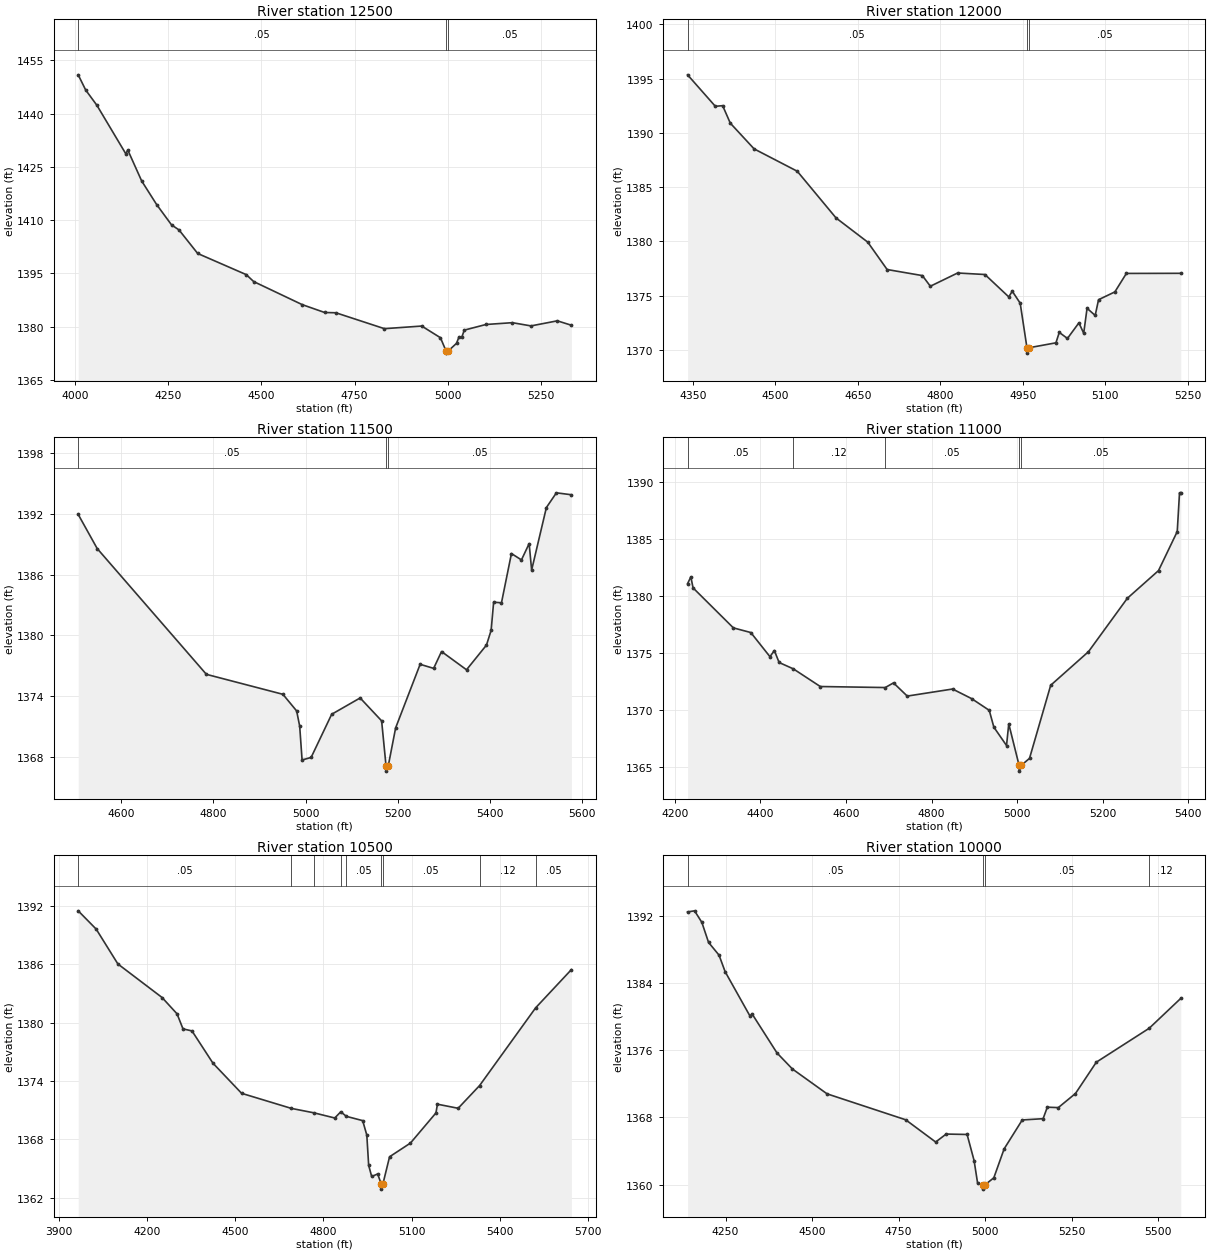
Type RM Length L Ch R = 1,12500,500,500,500
BEGIN DESCRIPTION:
HICKORY31 25.0
END DESCRIPTION:
XS GIS Cut Line= 3
      2765155.72     10177753.11      2766145.90     10177715.15
      2766346.89     10177452.54
#Sta/Elev= 30
  4009.1 1450.96  4029.1 1446.69  4059.1 1442.39  4136.9 1428.67  4141.9 1429.79
  4179.2 1421.05  4219.2 1414.42  4259.2 1408.68  4279.3 1407.25  4329.3 1400.62
  4459.4 1394.66  4479.4 1392.70  4609.5 1386.20  4669.5 1383.99  4699.6 1383.91
  4829.7 1379.43  4929.7 1380.17  4979.8 1376.88  4995.3 1373.04  4995.5 1372.54
  4999.5 1373.04  5022.9 1375.30  5029.2 1377.01  5037.4 1377.15  5043.7 1379.02
  5101.8 1380.61  5172.5 1381.12  5222.4 1380.21  5293.0 1381.64  5330.7 1380.40
#Mann=3,-1,0
  4009.1    0.05       0  4995.3    0.05       0  4999.5    0.05       0
Bank Sta=4995.3,4999.5
Exp/Cntr=0.3,0.1

Type RM Length L Ch R = 1,12000,500,500,500
BEGIN DESCRIPTION:
HICKORY31 24.0
END DESCRIPTION:
XS GIS Cut Line= 3
      2765805.69     10178553.11      2766322.52     10178143.45
      2766458.94     10177949.16
#Sta/Elev= 30
  4340.5 1395.34  4391.0 1392.44  4404.3 1392.50  4418.2 1390.89  4461.5 1388.52
  4540.0 1386.46  4610.5 1382.16  4668.2 1379.93  4703.4 1377.41  4767.5 1376.85
  4782.0 1375.87  4831.6 1377.09  4881.3 1376.95  4924.6 1374.89  4931.0 1375.41
  4945.4 1374.31  4957.7 1370.21  4958.0 1369.71  4962.0 1370.21  5010.4 1370.66
  5016.5 1371.62  5031.3 1371.06  5052.2 1372.50  5060.9 1371.54  5067.0 1373.84
  5081.8 1373.18  5087.9 1374.63  5117.6 1375.35  5138.5 1377.05  5237.4 1377.06
#Mann=3,-1,0
  4340.5    0.05       0  4957.7    0.05       0  4962.0    0.05       0
Bank Sta=4957.7,4962
Exp/Cntr=0.3,0.1

Type RM Length L Ch R = 1,11500,500,500,500
BEGIN DESCRIPTION:
HICKORY31 23.0
END DESCRIPTION:
XS GIS Cut Line= 3
      2766005.67     10178703.11      2766484.42     10178585.43
      2766705.69     10178053.09
#Sta/Elev= 30
  4507.0 1391.94  4548.2 1388.57  4785.0 1376.16  4950.9 1374.19  4980.7 1372.55
  4987.3 1371.05  4992.5 1367.71  5012.1 1367.96  5056.7 1372.22  5118.4 1373.83
  5165.0 1371.57  5174.6 1367.11  5174.9 1366.61  5179.3 1367.11  5195.4 1370.88
  5248.5 1377.15  5277.8 1376.75  5294.9 1378.41  5349.1 1376.61  5392.4 1379.05
  5402.5 1380.51  5407.9 1383.28  5424.9 1383.22  5446.5 1388.08  5468.2 1387.45
  5484.9 1389.06  5490.3 1386.45  5522.3 1392.62  5544.0 1394.07  5576.5 1393.88
#Mann=3,-1,0
  4507.0    0.05       0  5174.6    0.05       0  5179.3    0.05       0
Bank Sta=5174.6,5179.3
Exp/Cntr=0.3,0.1

Type RM Length L Ch R = 1,11000,500,500,500
BEGIN DESCRIPTION:
HICKORY31 22.0
END DESCRIPTION:
XS GIS Cut Line= 5
      2766325.57     10178851.52      2766836.30     10178658.51
      2766860.56     10178534.96      2766886.08     10178439.92
      2766705.67     10178103.09
#Sta/Elev= 30
  4229.7 1381.10  4237.3 1381.70  4242.6 1380.73  4336.7 1377.22  4377.5 1376.81
  4422.2 1374.69  4432.5 1375.23  4443.6 1374.18  4476.9 1373.62  4539.8 1372.07
  4691.6 1371.98  4710.9 1372.39  4743.0 1371.23  4848.9 1371.85  4893.3 1371.01
  4934.6 1369.98  4945.4 1368.50  4975.0 1366.89  4980.2 1368.79  5004.4 1365.14
  5004.7 1364.64  5009.1 1365.14  5028.7 1365.76  5078.2 1372.18  5166.5 1375.13
  5257.3 1379.82  5330.1 1382.25  5373.9 1385.68  5379.2 1389.08  5382.1 1389.08
#Mann=5,-1,0
  4229.7    0.05       0  4476.9    0.12       0  4691.6    0.05       0
  5004.4    0.05       0  5009.1    0.05       0
Bank Sta=5004.4,5009.1
Exp/Cntr=0.3,0.1

Type RM Length L Ch R = 1,10500,500,500,500
BEGIN DESCRIPTION:
HICKORY31 21.0
END DESCRIPTION:
XS GIS Cut Line= 3
      2766055.65     10178953.12      2767071.08     10178757.99
      2767705.67     10178653.11
#Sta/Elev= 30
  3966.0 1391.51  4027.1 1389.63  4101.0 1386.04  4251.2 1382.59  4302.1 1380.91
  4322.4 1379.36  4353.0 1379.15  4424.3 1375.83  4521.7 1372.73  4690.7 1371.18
  4767.9 1370.72  4838.5 1370.19  4859.0 1370.83  4877.8 1370.36  4933.4 1369.92
  4947.5 1368.43  4953.8 1365.32  4964.0 1364.17  4984.3 1364.43  4997.0 1363.37
  4997.3 1362.87  5002.0 1363.37  5024.9 1366.20  5095.9 1367.61  5182.6 1370.71
  5187.7 1371.61  5258.1 1371.19  5331.1 1373.53  5521.7 1381.53  5643.2 1385.46
#Mann=9,-1,0
  3966.0    0.05       0  4690.7    0.12       0  4767.9    0.05       0
  4859.0    0.12       0  4877.8    0.05       0  4997.0    0.05       0
  5002.0    0.05       0  5331.1    0.12       0  5521.7    0.05       0
Bank Sta=4997,5002
Exp/Cntr=0.3,0.1

Type RM Length L Ch R = 1,10000,349,349,349
BEGIN DESCRIPTION:
HICKORY31 20.0
END DESCRIPTION:
XS GIS Cut Line= 3
      2766355.65     10179103.11      2767207.37     10179219.22
      2767705.67     10178953.12
#Sta/Elev= 30
  4140.4 1392.47  4160.6 1392.60  4181.6 1391.23  4201.0 1388.84  4231.3 1387.32
  4248.9 1385.35  4321.3 1380.02  4326.3 1380.35  4398.7 1375.67  4443.2 1373.76
  4543.3 1370.80  4770.4 1367.71  4857.0 1365.06  4887.3 1366.01  4947.8 1365.96
  4968.0 1362.85  4978.1 1360.17  4994.1 1359.95  4994.5 1359.45  4999.1 1359.95
  5025.0 1360.80  5054.8 1364.25  5107.1 1367.69  5167.3 1367.84  5179.5 1369.21
  5211.2 1369.16  5260.8 1370.84  5321.0 1374.57  5473.7 1378.61  5564.9 1382.17
#Mann=4,-1,0
  4140.4    0.05       0  4994.1    0.05       0  4999.1    0.05       0
  5473.7    0.12       0
Bank Sta=4994.1,4999.1
Exp/Cntr=0.3,0.1

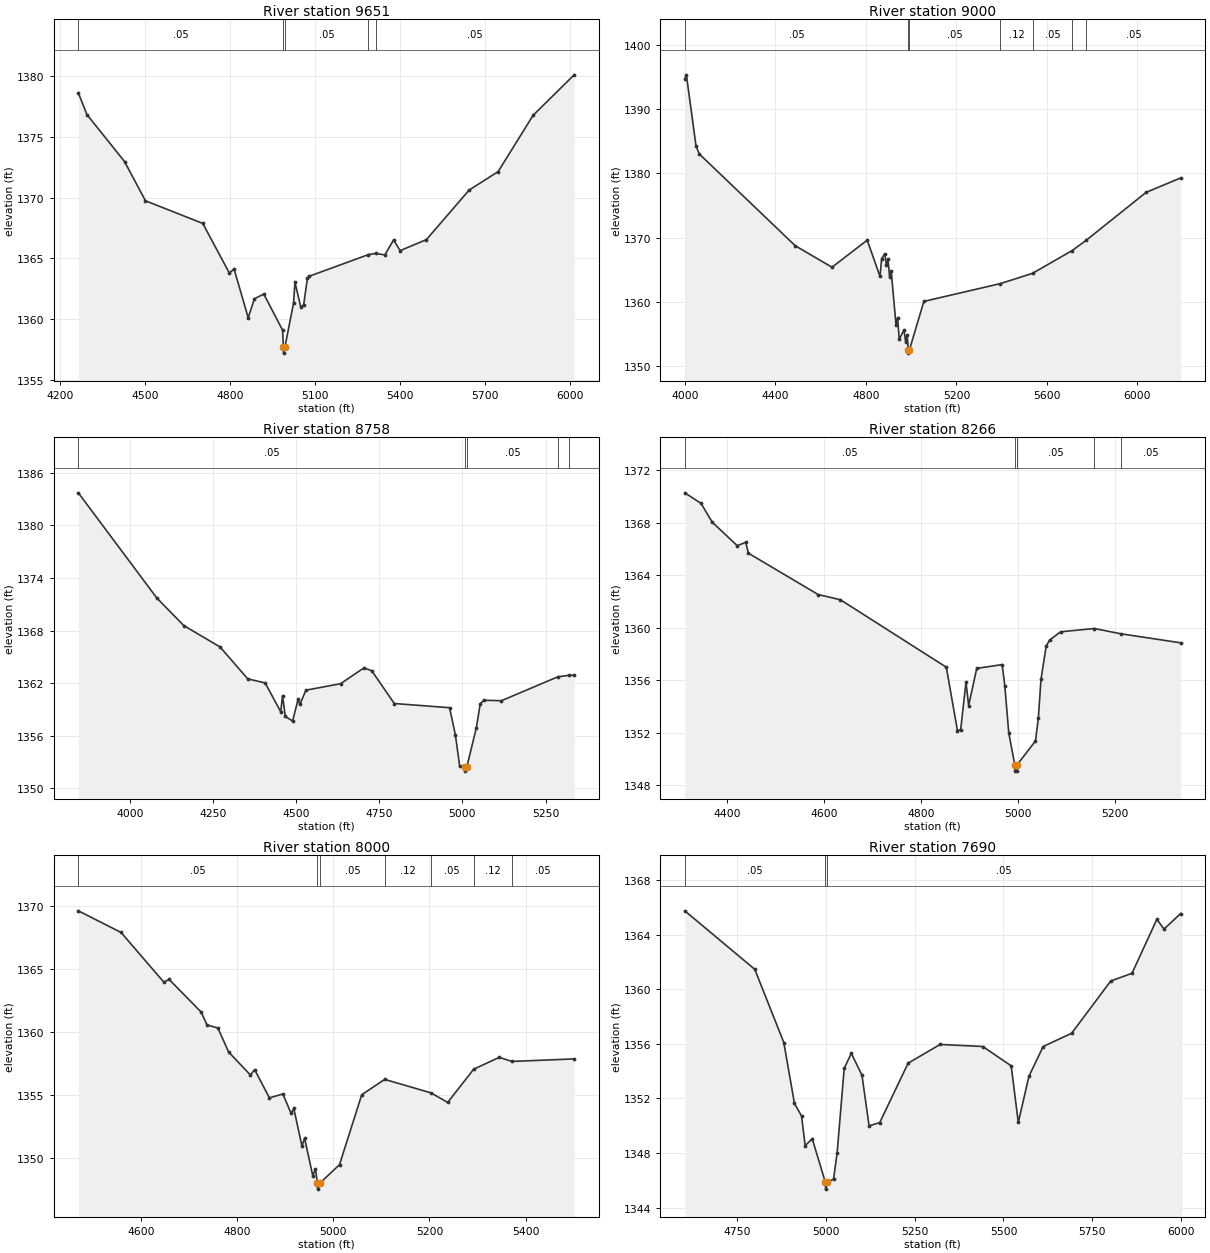
Type RM Length L Ch R = 1,9651,651,651,651
BEGIN DESCRIPTION:
HICKORY31 19.0
END DESCRIPTION:
XS GIS Cut Line= 3
      2766555.69     10179203.12      2767207.50     10179543.00
      2768197.57     10179760.15
#Sta/Elev= 30
  4264.9 1378.62  4295.2 1376.83  4427.8 1372.97  4501.7 1369.74  4703.7 1367.88
  4797.7 1363.79  4814.1 1364.14  4864.0 1360.12  4886.0 1361.68  4919.0 1362.07
  4985.2 1359.10  4988.3 1357.71  4988.7 1357.21  4993.5 1357.71  5023.8 1361.31
  5028.9 1363.04  5049.3 1361.01  5059.6 1361.18  5072.7 1363.35  5080.0 1363.54
  5287.5 1365.31  5314.3 1365.41  5345.9 1365.29  5376.9 1366.52  5399.9 1365.64
  5492.7 1366.55  5643.1 1370.62  5745.5 1372.14  5868.8 1376.77  6013.6 1380.10
#Mann=5,-1,0
  4264.9    0.05       0  4988.3    0.05       0  4993.5    0.05       0
  5287.5    0.12       0  5314.3    0.05       0
Bank Sta=4988.3,4993.5
Exp/Cntr=0.3,0.1

Type RM Length L Ch R = 1,9000,242,242,242
BEGIN DESCRIPTION:
HICKORY31 18.0
END DESCRIPTION:
XS GIS Cut Line= 3
      2766305.72     10179203.14      2767019.60     10179903.69
      2768208.00     10179826.61
#Sta/Elev= 30
  3999.8 1394.78  4006.8 1395.38  4049.3 1384.31  4063.4 1383.05  4487.7 1368.72
  4650.3 1365.36  4805.9 1369.59  4862.5 1363.92  4869.5 1366.67  4883.6 1367.47
  4890.8 1365.68  4897.8 1366.59  4904.9 1363.82  4911.9 1364.77  4933.2 1356.34
  4940.2 1357.51  4947.3 1354.12  4968.5 1355.56  4975.6 1353.73  4982.6 1354.75
  4987.2 1352.46  4987.6 1351.96  4992.4 1352.46  5056.2 1360.03  5394.8 1362.81
  5536.6 1364.41  5711.7 1367.97  5774.5 1369.59  6038.3 1377.04  6190.9 1379.29
#Mann=7,-1,0
  3999.8    0.05       0  4987.2    0.05       0  4992.4    0.05       0
  5394.8    0.12       0  5536.6    0.05       0  5711.7    0.12       0
  5774.5    0.05       0
Bank Sta=4987.2,4992.4
Exp/Cntr=0.3,0.1

Type RM Length L Ch R = 1,8758,492,492,492
BEGIN DESCRIPTION:
HICKORY31 17.0
END DESCRIPTION:
XS GIS Cut Line= 3
      2766105.66     10179703.10      2767075.27     10180127.52
      2767480.68     10179978.11
#Sta/Elev= 30
  3845.6 1383.72  4081.4 1371.72  4162.5 1368.57  4271.4 1366.13  4355.0 1362.48
  4407.3 1362.02  4454.0 1358.72  4459.5 1360.56  4467.8 1358.19  4489.7 1357.67
  4506.3 1360.15  4511.7 1359.56  4529.7 1361.19  4634.1 1361.93  4704.3 1363.74
  4727.7 1363.41  4795.3 1359.67  4961.6 1359.19  4979.1 1356.07  4992.1 1352.50
  5008.4 1352.45  5008.8 1351.95  5013.6 1352.45  5042.3 1356.93  5053.7 1359.64
  5064.3 1360.04  5117.6 1359.99  5287.1 1362.72  5321.0 1362.89  5336.1 1362.90
#Mann=5,-1,0
  3845.6    0.05       0  5008.4    0.05       0  5013.6    0.05       0
  5287.1    0.12       0  5321.0    0.05       0
Bank Sta=5008.4,5013.6
Exp/Cntr=0.3,0.1

Type RM Length L Ch R = 1,8266,266,266,266
BEGIN DESCRIPTION:
Mapping XS 457c2c6b
END DESCRIPTION:
XS GIS Cut Line= 3
      2766259.34     10180014.69      2767092.63     10180396.62
      2767196.78     10180396.62
#Sta/Elev= 30
  4313.6 1370.27  4346.9 1369.47  4370.0 1368.04  4421.5 1366.24  4439.0 1366.50
  4444.5 1365.67  4588.0 1362.52  4634.0 1362.12  4852.0 1356.98  4875.0 1352.14
  4881.6 1352.23  4892.5 1355.84  4898.0 1354.06  4914.6 1356.89  4967.0 1357.18
  4972.5 1355.54  4980.6 1351.97  4992.9 1349.56  4993.3 1349.06  4997.7 1349.06
  4998.1 1349.56  5035.6 1351.36  5041.5 1353.12  5047.0 1356.08  5057.6 1358.58
  5064.5 1359.04  5087.5 1359.68  5156.7 1359.93  5210.9 1359.53  5334.4 1358.84
#Mann=5,-1,0
  4313.6    0.05       0  4992.9    0.05       0  4998.1    0.05       0
  5156.7    0.12       0  5210.9    0.05       0
Bank Sta=4992.9,4998.1
Exp/Cntr=0.3,0.1

Type RM Length L Ch R = 1,8000,310,310,310
BEGIN DESCRIPTION:
HICKORY31 16.0
END DESCRIPTION:
XS GIS Cut Line= 3
      2766205.72     10180703.09      2766682.79     10180471.28
      2767180.66     10180528.11
#Sta/Elev= 30
  4469.6 1369.65  4558.5 1367.93  4647.4 1363.98  4658.5 1364.19  4725.3 1361.59
  4737.3 1360.57  4759.9 1360.33  4782.4 1358.41  4827.6 1356.59  4836.4 1357.02
  4867.1 1354.77  4895.2 1355.08  4912.2 1353.53  4917.8 1353.93  4934.8 1350.94
  4940.3 1351.56  4957.3 1348.58  4962.9 1349.12  4966.9 1348.01  4967.4 1347.51
  4972.8 1348.01  5013.0 1349.46  5059.2 1355.02  5107.0 1356.24  5203.0 1355.17
  5238.0 1354.41  5292.1 1357.05  5345.1 1357.99  5371.6 1357.67  5501.1 1357.87
#Mann=7,-1,0
  4469.6    0.05       0  4966.9    0.05       0  4972.8    0.05       0
  5107.0    0.12       0  5203.0    0.05       0  5292.1    0.12       0
  5371.6    0.05       0
Bank Sta=4966.9,4972.8
Exp/Cntr=0.3,0.1

Type RM Length L Ch R = 1,7690,395,395,395
BEGIN DESCRIPTION:
Mapping XS e1521deb
END DESCRIPTION:
XS GIS Cut Line= 3
      2766393.88     10180781.09      2766658.61     10180720.33
      2767782.51     10180734.72
#Sta/Elev= 30
  4603.1 1365.76  4800.1 1361.47  4881.8 1356.10  4911.8 1351.63  4931.8 1350.71
  4941.8 1348.54  4961.8 1349.04  4998.8 1345.85  4999.3 1345.35  5004.7 1345.85
  5021.8 1346.09  5031.8 1347.99  5051.8 1354.21  5071.8 1355.31  5101.8 1353.70
  5121.8 1349.99  5151.8 1350.23  5231.8 1354.59  5321.8 1355.96  5441.8 1355.81
  5521.8 1354.39  5541.8 1350.24  5571.8 1353.63  5611.8 1355.81  5691.9 1356.78
  5801.9 1360.61  5861.9 1361.18  5931.9 1365.14  5951.9 1364.42  5998.7 1365.56
#Mann=3,-1,0
  4603.1    0.05       0  4998.8    0.05       0  5004.7    0.05       0
Bank Sta=4998.8,5004.7
Exp/Cntr=0.3,0.1