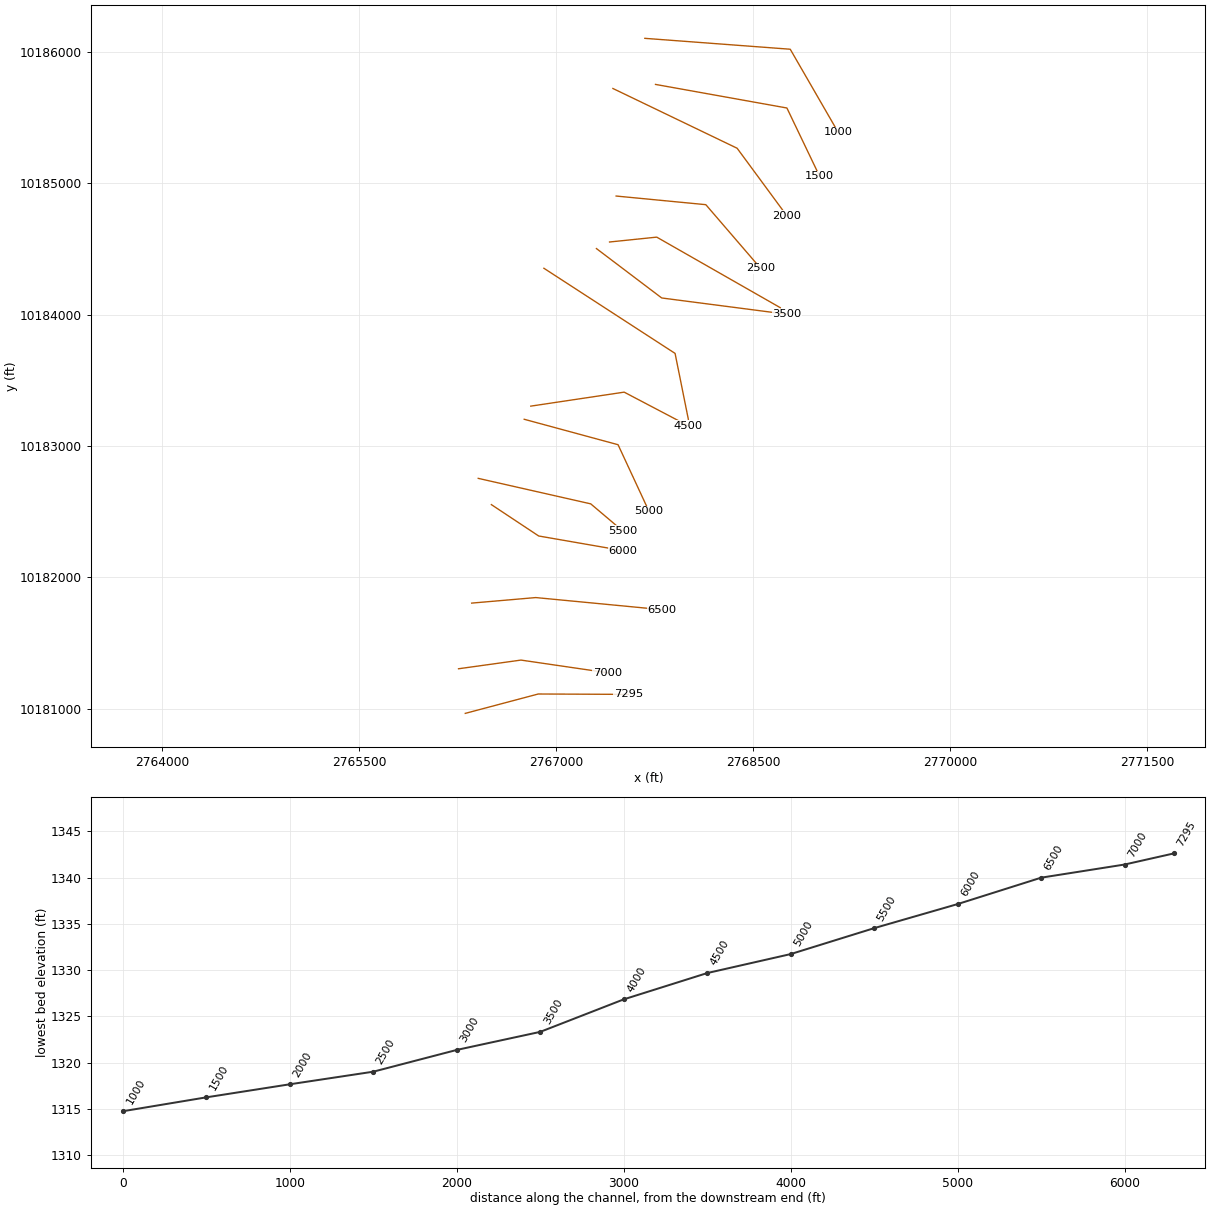
HEC-RAS study HICKORY31.prj: HICKORY31 Base Level Engineering

--- HICKORY31.g01 (geometry) --- (continued)

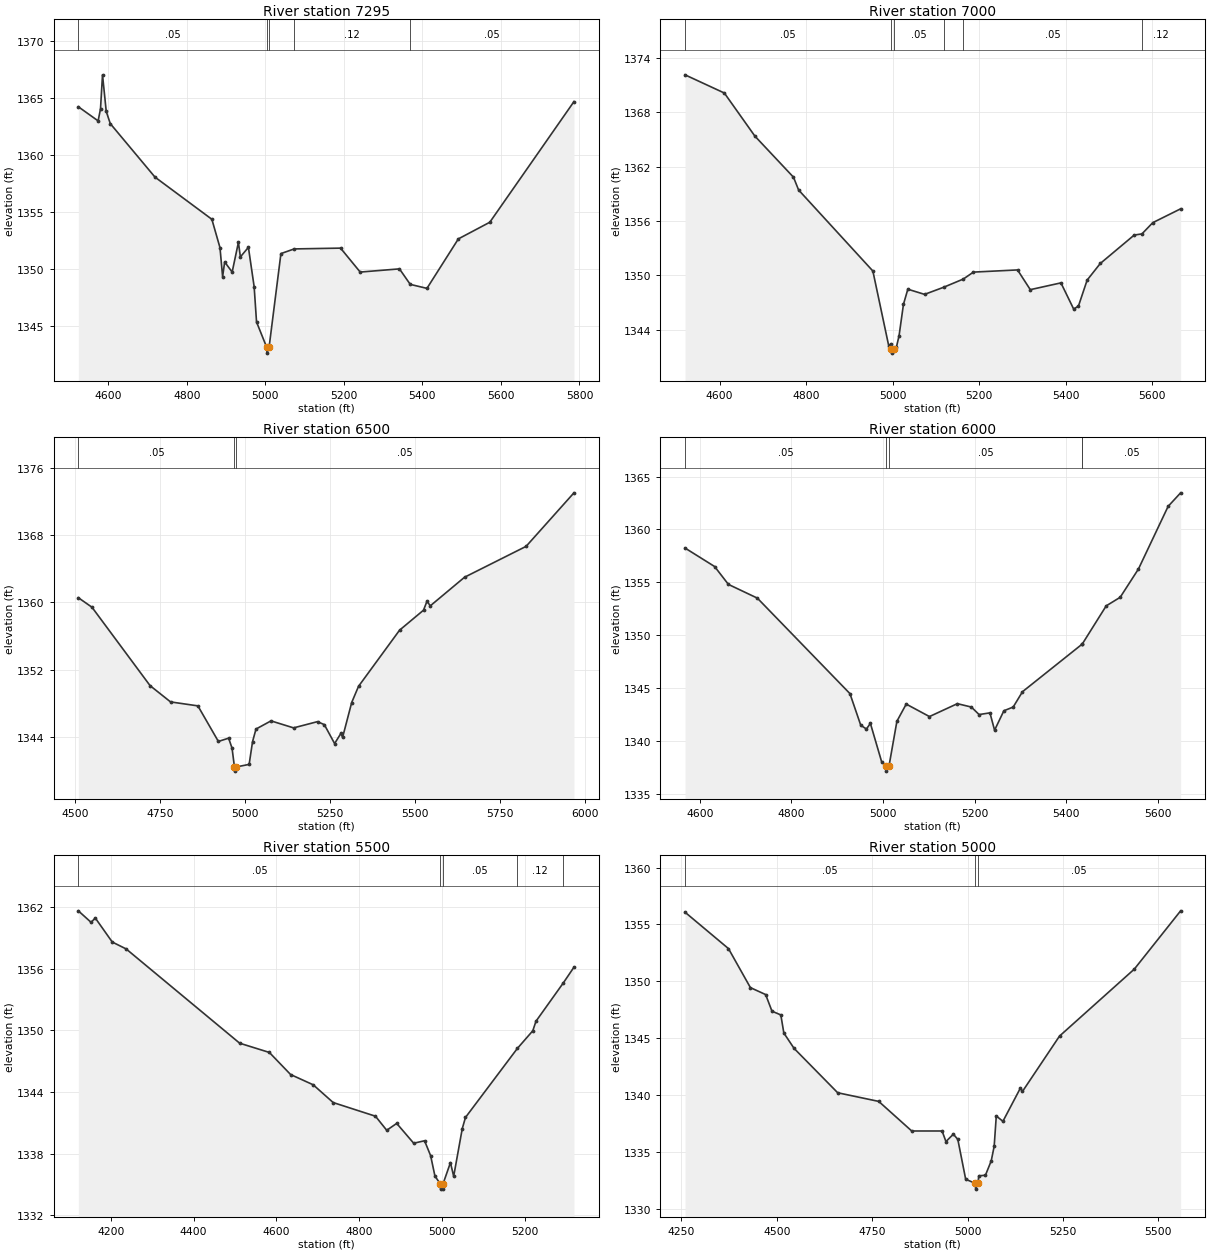
Type RM Length L Ch R = 1,7295,295,295,295
BEGIN DESCRIPTION:
Mapping XS d5cfebc6
END DESCRIPTION:
XS GIS Cut Line= 3
      2766307.00     10180963.37      2766862.60     10181110.95
      2767550.03     10181108.01
#Sta/Elev= 30
  4523.6 1364.22  4574.0 1362.98  4580.1 1364.03  4585.2 1367.02  4594.7 1363.81
  4605.0 1362.74  4718.8 1358.05  4863.7 1354.35  4884.4 1351.86  4891.1 1349.31
  4896.3 1350.61  4915.4 1349.72  4931.3 1352.32  4936.4 1351.05  4956.8 1351.89
  4971.4 1348.44  4977.5 1345.34  5003.5 1343.11  5004.0 1342.61  5009.4 1343.11
  5039.6 1351.34  5073.4 1351.75  5191.5 1351.82  5241.5 1349.72  5341.5 1350.00
  5369.0 1348.64  5411.5 1348.29  5491.5 1352.63  5571.6 1354.09  5785.9 1364.67
#Mann=5,-1,0
  4523.6    0.05       0  5003.5    0.05       0  5009.4    0.05       0
  5073.4    0.12       0  5369.0    0.05       0
Bank Sta=5003.5,5009.4
Exp/Cntr=0.3,0.1

Type RM Length L Ch R = 1,7000,500,500,500
BEGIN DESCRIPTION:
HICKORY31 14.0
END DESCRIPTION:
XS GIS Cut Line= 3
      2766255.69     10181303.11      2766731.11     10181369.24
      2767389.41     10181272.94
#Sta/Elev= 30
  4520.0 1372.15  4610.9 1370.14  4681.5 1365.38  4770.7 1360.84  4782.5 1359.43
  4954.1 1350.48  4990.7 1342.23  4995.7 1342.45  4996.8 1341.91  4997.3 1341.41
  5002.7 1341.91  5008.7 1342.10  5014.7 1343.35  5024.8 1346.80  5034.9 1348.47
  5073.6 1347.90  5117.4 1348.68  5163.0 1349.59  5186.5 1350.36  5288.4 1350.60
  5317.9 1348.42  5388.7 1349.17  5418.1 1346.28  5429.1 1346.60  5449.3 1349.48
  5479.6 1351.31  5558.0 1354.45  5575.9 1354.58  5600.9 1355.82  5665.3 1357.35
#Mann=6,-1,0
  4520.0    0.05       0  4996.8    0.05       0  5002.7    0.05       0
  5117.4    0.12       0  5163.0    0.05       0  5575.9    0.12       0
Bank Sta=4996.8,5002.7
Exp/Cntr=0.3,0.1

Type RM Length L Ch R = 1,6500,500,500,500
BEGIN DESCRIPTION:
HICKORY31 13.0
END DESCRIPTION:
XS GIS Cut Line= 3
      2766355.68     10181803.11      2766843.66     10181845.29
      2767805.66     10181753.11
#Sta/Elev= 30
  4510.2 1360.56  4550.3 1359.43  4721.0 1350.13  4781.2 1348.20  4861.5 1347.73
  4921.7 1343.51  4951.8 1343.90  4961.9 1342.71  4968.9 1340.49  4969.4 1339.99
  4974.9 1340.49  5012.1 1340.79  5022.1 1343.49  5032.2 1344.98  5076.3 1345.95
  5142.7 1345.12  5213.0 1345.86  5233.1 1345.50  5263.2 1343.26  5281.6 1344.46
  5286.7 1344.00  5313.4 1348.13  5333.5 1350.05  5454.1 1356.71  5524.4 1359.08
  5534.5 1360.13  5544.5 1359.60  5645.0 1362.99  5825.8 1366.65  5966.4 1373.00
#Mann=3,-1,0
  4510.2    0.05       0  4968.9    0.05       0  4974.9    0.05       0
Bank Sta=4968.9,4974.9
Exp/Cntr=0.3,0.1

Type RM Length L Ch R = 1,6000,500,500,500
BEGIN DESCRIPTION:
HICKORY31 12.0
END DESCRIPTION:
XS GIS Cut Line= 3
      2766505.72     10182553.09      2766866.04     10182314.24
      2767505.66     10182203.12
#Sta/Elev= 30
  4567.7 1358.24  4632.3 1356.49  4662.4 1354.80  4725.6 1353.50  4927.6 1344.47
  4951.2 1341.48  4963.6 1341.12  4972.2 1341.66  4996.8 1338.02  5006.6 1337.64
  5007.1 1337.14  5012.9 1337.64  5030.1 1341.86  5050.4 1343.48  5101.1 1342.30
  5162.0 1343.52  5192.5 1343.20  5209.4 1342.49  5233.1 1342.65  5243.2 1341.01
  5263.5 1342.85  5283.8 1343.20  5304.1 1344.65  5434.3 1349.15  5434.7 1349.17
  5486.8 1352.77  5517.3 1353.58  5557.2 1356.26  5621.9 1362.18  5649.2 1363.46
#Mann=5,-1,0
  4567.7    0.05       0  5006.6    0.05       0  5012.9    0.05       0
  5434.3    0.12       0  5434.7    0.05       0
Bank Sta=5006.6,5012.9
Exp/Cntr=0.3,0.1

Type RM Length L Ch R = 1,5500,500,500,500
BEGIN DESCRIPTION:
HICKORY31 11.0
END DESCRIPTION:
XS GIS Cut Line= 3
      2766405.69     10182753.11      2767262.46     10182558.94
      2767505.67     10182353.13
#Sta/Elev= 30
  4121.5 1361.64  4152.3 1360.52  4162.5 1360.94  4203.5 1358.60  4237.0 1357.93
  4511.2 1348.75  4582.9 1347.85  4634.2 1345.70  4688.8 1344.70  4737.1 1342.97
  4839.2 1341.64  4866.4 1340.27  4890.5 1340.94  4931.5 1339.01  4957.8 1339.25
  4972.5 1337.79  4982.8 1335.82  4995.9 1335.04  4996.4 1334.54  5001.8 1334.54
  5002.3 1335.04  5020.3 1337.12  5028.1 1335.79  5048.9 1340.44  5056.6 1341.52
  5181.9 1348.24  5219.2 1349.96  5226.9 1350.89  5293.1 1354.63  5318.6 1356.15
#Mann=5,-1,0
  4121.5    0.05       0  4995.9    0.05       0  5002.3    0.05       0
  5181.9    0.12       0  5293.1    0.05       0
Bank Sta=4995.9,5002.3
Exp/Cntr=0.3,0.1

Type RM Length L Ch R = 1,5000,500,500,500
BEGIN DESCRIPTION:
HICKORY31 10.0
END DESCRIPTION:
XS GIS Cut Line= 3
      2766755.71     10183203.10      2767470.42     10183009.37
      2767705.70     10182503.07
#Sta/Elev= 30
  4259.5 1356.08  4373.4 1352.88  4430.9 1349.45  4470.8 1348.84  4487.4 1347.38
  4510.6 1347.05  4518.5 1345.46  4545.3 1344.11  4659.6 1340.21  4767.2 1339.45
  4853.6 1336.85  4933.2 1336.85  4943.3 1335.92  4962.7 1336.57  4974.4 1336.11
  4995.0 1332.61  5020.7 1332.24  5021.2 1331.74  5027.1 1332.24  5029.4 1332.91
  5046.8 1332.96  5062.0 1334.23  5069.7 1335.51  5075.2 1338.17  5092.6 1337.70
  5138.4 1340.62  5143.9 1340.33  5240.9 1345.19  5437.0 1351.08  5558.3 1356.20
#Mann=3,-1,0
  4259.5    0.05       0  5020.7    0.05       0  5027.1    0.05       0
Bank Sta=5020.7,5027.1
Exp/Cntr=0.3,0.1

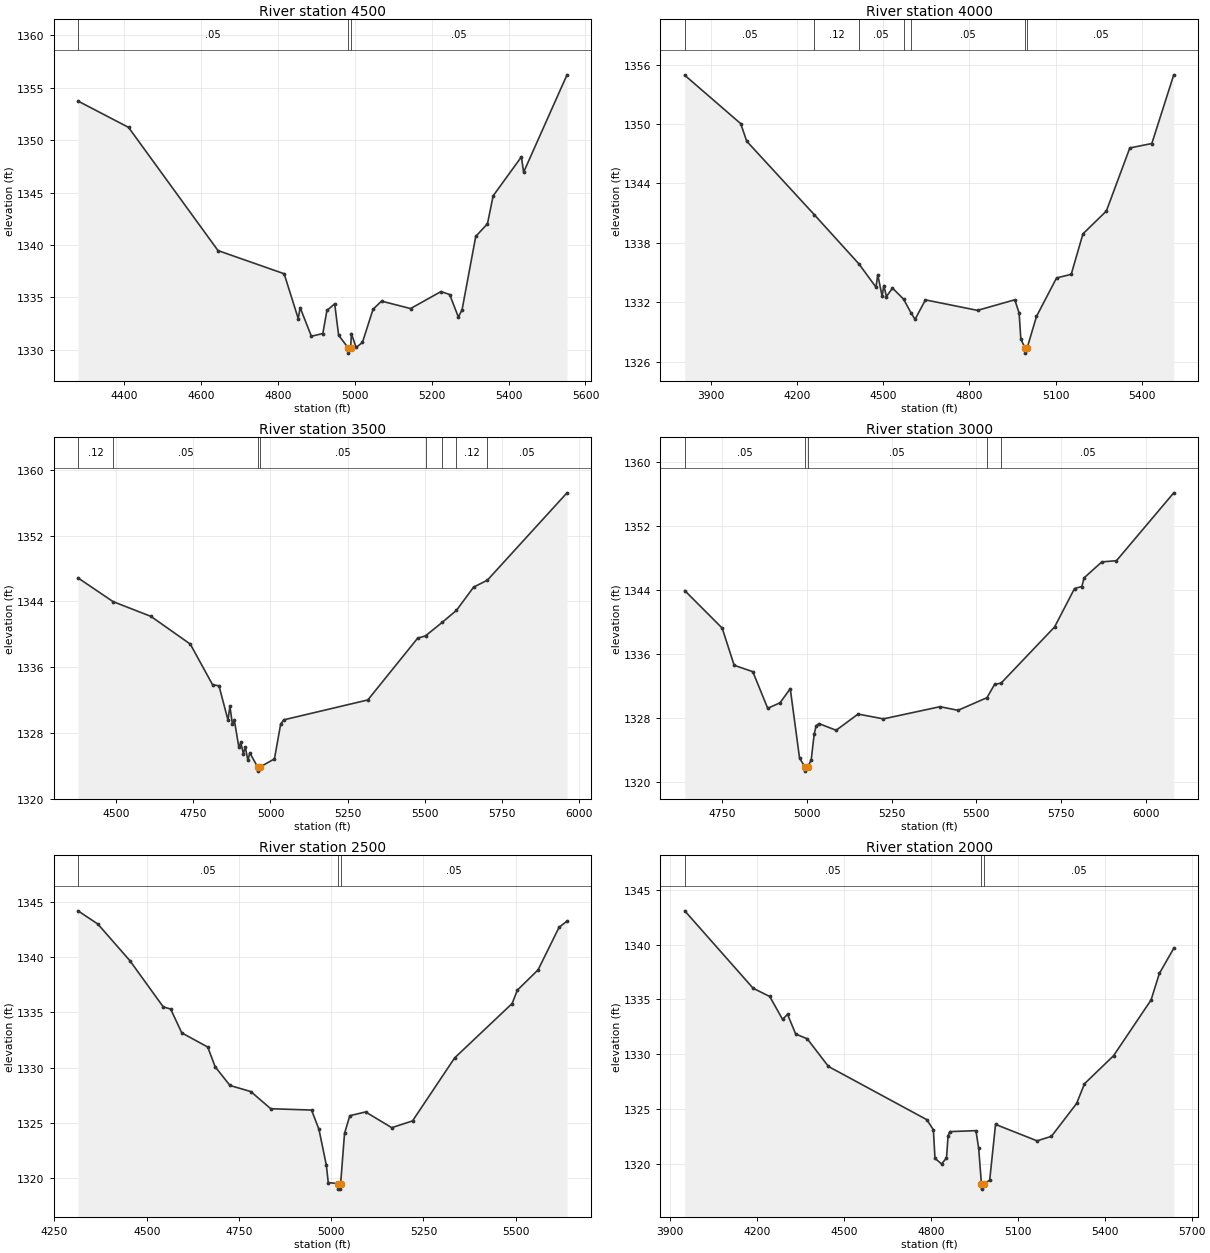
Type RM Length L Ch R = 1,4500,500,500,500
BEGIN DESCRIPTION:
HICKORY31 9.0
END DESCRIPTION:
XS GIS Cut Line= 3
      2766805.71     10183303.12      2767516.97     10183409.68
      2768005.71     10183153.10
#Sta/Elev= 30
  4280.8 1353.73  4412.2 1351.22  4644.8 1339.47  4816.7 1337.26  4853.3 1332.99
  4858.3 1334.03  4887.5 1331.30  4917.3 1331.56  4927.9 1333.76  4948.1 1334.39
  4958.3 1331.40  4983.2 1330.19  4983.7 1329.69  4989.7 1330.19  4991.5 1331.55
  5003.8 1330.23  5020.2 1330.71  5047.9 1333.88  5069.9 1334.65  5145.4 1333.94
  5224.4 1335.56  5247.0 1335.28  5269.6 1333.13  5279.2 1333.82  5314.8 1340.82
  5345.3 1342.03  5360.0 1344.69  5433.5 1348.41  5439.2 1346.94  5552.0 1356.23
#Mann=3,-1,0
  4280.8    0.05       0  4983.2    0.05       0  4989.7    0.05       0
Bank Sta=4983.2,4989.7
Exp/Cntr=0.3,0.1

Type RM Length L Ch R = 1,4000,500,500,500
BEGIN DESCRIPTION:
HICKORY31 8.0
END DESCRIPTION:
XS GIS Cut Line= 3
      2766905.67     10184353.12      2767904.75     10183704.63
      2768005.69     10183203.09
#Sta/Elev= 30
  3808.9 1354.93  4003.7 1350.04  4024.8 1348.26  4260.6 1340.82  4415.3 1335.87
  4475.0 1333.51  4480.9 1334.78  4496.1 1332.61  4502.0 1333.68  4511.2 1332.57
  4532.3 1333.42  4570.8 1332.31  4596.6 1330.93  4610.8 1330.26  4647.0 1332.23
  4828.3 1331.17  4958.1 1332.24  4973.3 1330.89  4979.2 1328.26  4994.3 1327.35
  4994.8 1326.85  5000.9 1327.35  5033.7 1330.56  5103.6 1334.45  5154.6 1334.81
  5195.4 1338.90  5277.0 1341.21  5358.6 1347.58  5435.3 1348.03  5511.6 1354.97
#Mann=7,-1,0
  3808.9    0.05       0  4260.6    0.12       0  4415.3    0.05       0
  4570.8    0.12       0  4596.6    0.05       0  4994.3    0.05       0
  5000.9    0.05       0
Bank Sta=4994.3,5000.9
Exp/Cntr=0.3,0.1

Type RM Length L Ch R = 1,3500,500,500,500
BEGIN DESCRIPTION:
HICKORY31 7.0
END DESCRIPTION:
XS GIS Cut Line= 3
      2767305.66     10184503.13      2767802.94     10184126.85
      2768755.64     10184003.12
#Sta/Elev= 30
  4376.4 1346.85  4490.2 1343.96  4612.6 1342.17  4740.1 1338.80  4812.3 1333.86
  4833.2 1333.72  4862.3 1329.56  4868.6 1331.23  4876.8 1329.02  4883.1 1329.50
  4897.7 1326.22  4903.9 1326.83  4912.2 1325.46  4918.5 1326.28  4926.8 1324.64
  4933.0 1325.56  4958.5 1323.84  4959.0 1323.34  4965.9 1323.84  5012.9 1324.83
  5033.0 1329.06  5043.1 1329.58  5315.4 1332.00  5476.7 1339.51  5502.4 1339.80
  5556.7 1341.45  5602.6 1342.90  5658.2 1345.73  5702.7 1346.57  5960.7 1357.20
#Mann=8,-1,0
  4376.4    0.12       0  4490.2    0.05       0  4958.5    0.05       0
  4965.9    0.05       0  5502.4    0.12       0  5556.7    0.05       0
  5602.6    0.12       0  5702.7    0.05       0
Bank Sta=4958.5,4965.9
Exp/Cntr=0.3,0.1

Type RM Length L Ch R = 1,3000,500,500,500
BEGIN DESCRIPTION:
HICKORY31 6.0
END DESCRIPTION:
XS GIS Cut Line= 3
      2767405.67     10184553.11      2767765.07     10184590.16
      2768705.66     10184053.13
#Sta/Elev= 30
  4638.7 1343.92  4749.3 1339.24  4784.7 1334.60  4839.8 1333.80  4883.8 1329.23
  4920.2 1329.92  4950.4 1331.68  4977.8 1323.02  4994.1 1321.89  4994.6 1321.39
  5001.5 1321.89  5012.2 1322.78  5021.1 1326.03  5026.9 1327.06  5035.3 1327.32
  5085.9 1326.49  5150.7 1328.51  5225.6 1327.91  5392.7 1329.43  5445.9 1328.98
  5531.5 1330.56  5553.9 1332.21  5573.3 1332.38  5731.1 1339.38  5790.1 1344.18
  5811.7 1344.43  5818.3 1345.51  5870.7 1347.50  5913.9 1347.65  6083.1 1356.12
#Mann=5,-1,0
  4638.7    0.05       0  4994.1    0.03       0  5001.5    0.05       0
  5531.5    0.12       0  5573.3    0.05       0
Bank Sta=4994.1,5001.5
Exp/Cntr=0.3,0.1

Type RM Length L Ch R = 1,2500,500,500,500
BEGIN DESCRIPTION:
HICKORY31 5.0
END DESCRIPTION:
XS GIS Cut Line= 3
      2767455.71     10184903.11      2768138.85     10184837.34
      2768555.67     10184353.13
#Sta/Elev= 30
  4313.7 1344.17  4367.4 1342.98  4454.3 1339.67  4544.7 1335.50  4564.8 1335.30
  4595.0 1333.15  4665.3 1331.87  4685.4 1330.09  4725.6 1328.40  4782.0 1327.85
  4836.1 1326.30  4946.6 1326.18  4966.7 1324.44  4986.8 1321.19  4991.9 1319.63
  5018.0 1319.54  5018.5 1319.04  5025.0 1319.04  5025.5 1319.54  5036.0 1324.07
  5050.3 1325.67  5093.1 1326.01  5163.9 1324.59  5220.3 1325.20  5334.4 1330.89
  5490.2 1335.80  5504.5 1337.01  5560.5 1338.84  5617.5 1342.69  5638.9 1343.24
#Mann=3,-1,0
  4313.7    0.05       0  5018.0    0.05       0  5025.5    0.05       0
Bank Sta=5018,5025.5
Exp/Cntr=0.3,0.1

Type RM Length L Ch R = 1,2000,500,500,500
BEGIN DESCRIPTION:
HICKORY31 4.0
END DESCRIPTION:
XS GIS Cut Line= 3
      2767431.37     10185722.15      2768377.28     10185267.05
      2768755.67     10184753.12
#Sta/Elev= 30
  3950.3 1343.09  4186.4 1336.02  4243.6 1335.27  4288.0 1333.18  4305.1 1333.64
  4333.3 1331.84  4373.0 1331.41  4446.4 1328.88  4785.9 1324.02  4808.5 1323.10
  4814.1 1320.49  4836.7 1319.98  4853.8 1320.52  4859.3 1322.54  4865.1 1322.93
  4955.4 1323.02  4964.9 1321.41  4974.3 1318.18  4974.8 1317.68  4981.8 1318.18
  5002.9 1318.49  5023.1 1323.59  5166.3 1322.09  5216.0 1322.50  5302.9 1325.50
  5330.1 1327.30  5430.4 1329.86  5559.9 1334.95  5588.5 1337.37  5638.2 1339.67
#Mann=3,-1,0
  3950.3    0.05       0  4974.3    0.05       0  4981.8    0.05       0
Bank Sta=4974.3,4981.8
Exp/Cntr=0.3,0.1

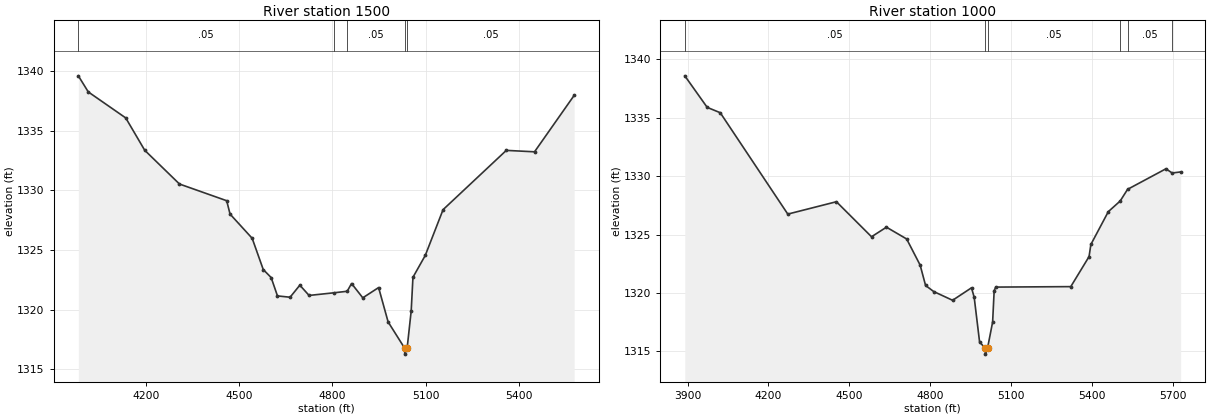
Type RM Length L Ch R = 1,1500,500,500,500
BEGIN DESCRIPTION:
HICKORY31 3.0
END DESCRIPTION:
XS GIS Cut Line= 3
      2767755.66     10185753.12      2768756.37     10185573.54
      2769005.70     10185053.08
#Sta/Elev= 30
  3983.3 1339.60  4015.3 1338.25  4135.7 1336.07  4196.7 1333.36  4308.4 1330.53
  4460.2 1329.13  4471.0 1328.01  4542.1 1325.98  4577.7 1323.36  4603.1 1322.69
  4623.4 1321.15  4664.0 1321.04  4695.3 1322.05  4725.0 1321.19  4804.5 1321.41
  4847.6 1321.54  4861.5 1322.19  4897.7 1320.99  4948.5 1321.85  4979.1 1318.97
  5032.2 1316.77  5032.7 1316.27  5040.2 1316.77  5053.3 1319.90  5058.9 1322.71
  5098.6 1324.55  5155.7 1328.38  5359.0 1333.35  5449.7 1333.23  5577.1 1337.96
#Mann=5,-1,0
  3983.3    0.05       0  4804.5    0.12       0  4847.6    0.05       0
  5032.2    0.03       0  5040.2    0.05       0
Bank Sta=5032.2,5040.2
Exp/Cntr=0.3,0.1

Type RM Length L Ch R = 1,1000,0,0,0
BEGIN DESCRIPTION:
HICKORY31 2.0
END DESCRIPTION:
XS GIS Cut Line= 3
      2767674.50     10186104.07      2768781.69     10186021.09
      2769146.69     10185388.77
#Sta/Elev= 30
  3889.7 1338.60  3972.8 1335.90  4021.3 1335.44  4272.0 1326.76  4452.5 1327.82
  4582.8 1324.82  4638.2 1325.64  4713.2 1324.63  4763.3 1322.39  4783.4 1320.65
  4813.5 1320.13  4883.7 1319.38  4953.9 1320.45  4963.9 1319.63  4983.9 1315.81
  5005.1 1315.27  5005.6 1314.77  5013.3 1315.27  5032.3 1317.52  5038.0 1320.20
  5043.8 1320.51  5322.4 1320.55  5390.2 1323.12  5397.0 1324.16  5461.7 1326.97
  5505.7 1327.88  5533.2 1328.88  5675.6 1330.64  5698.6 1330.28  5730.1 1330.37
#Mann=6,-1,0
  3889.7    0.05       0  5005.1    0.05       0  5013.3    0.05       0
  5505.7    0.12       0  5533.2    0.05       0  5698.6    0.12       0
Bank Sta=5005.1,5013.3
Exp/Cntr=0.3,0.1

Chan Stop Cuts=-1