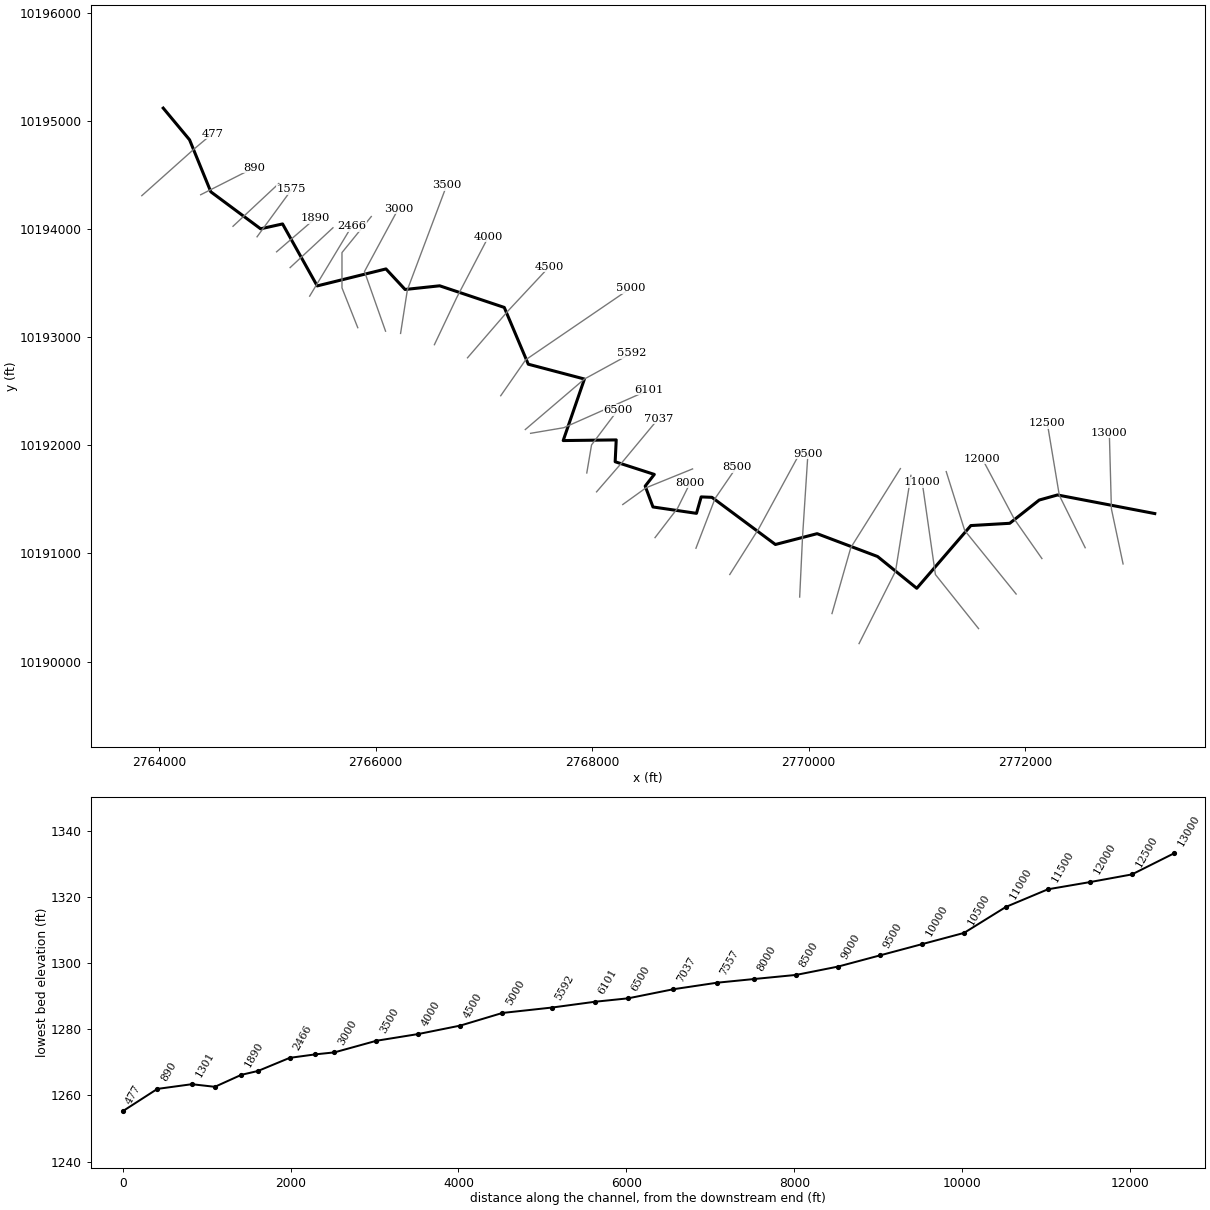
--- HICKORY33.prj (project) ---

Proj Title=HICKORY33 Base Level Engineering
Current Plan=p01
Default Exp/Contr=0.3,0.1
English Units
Geom File=g01
Flow File=f01
Plan File=p01
BEGIN DESCRIPTION:
HICKORY33
END DESCRIPTION:

--- HICKORY33.p01 (plan) ---

Plan Title=Multiple Run
Short Identifier=Multiple
Geom File=g01
Flow File=f01
Subcritical Flow
K Sum by GR= 0
Std Step Tol= 0.01
Critical Tol= 0.01
Num of Std Step Trials= 20
Max Error Tol= 0.3
Flow Tol Ratio= 0.001
Split Flow NTrial= 30
Split Flow Tol= 0.02
Split Flow Ratio= 0.02
Log Output Level= 0
Friction Slope Method= 1
Unsteady Friction Slope Method= 2
Unsteady Bridges Friction Slope Method= 1
Parabolic Critical Depth
Global Vel Dist=  1 , 1 , 1
Global Log Level= 0
CheckData=True
Encroach Param= -1, 0, 0, 0
BEGIN DESCRIPTION:
Multiple Run
END DESCRIPTION:

--- HICKORY33.f01 (steady flow) ---

Flow Title=Multiple
Number of Profiles=7
Profile Names=10-year,25-year,50-year,1pct_min,100-year,1pct_plu,500-year
River Rch & RM= HICKORY33,Reach-1,13000
     456     741     767     538     994    1835    1326
River Rch & RM= HICKORY33,Reach-1,4000
     598     995    1028     691    1346    2624    1800
Boundary for River Rch & Prof#=HICKORY33,Reach-1,1
Up Type=0
Dn Type=3
Dn Slope=0.005
Boundary for River Rch & Prof#=HICKORY33,Reach-1,2
Up Type=0
Dn Type=3
Dn Slope=0.005
Boundary for River Rch & Prof#=HICKORY33,Reach-1,3
Up Type=0
Dn Type=3
Dn Slope=0.005
Boundary for River Rch & Prof#=HICKORY33,Reach-1,4
Up Type=0
Dn Type=3
Dn Slope=0.005
Boundary for River Rch & Prof#=HICKORY33,Reach-1,5
Up Type=0
Dn Type=3
Dn Slope=0.005
Boundary for River Rch & Prof#=HICKORY33,Reach-1,6
Up Type=0
Dn Type=3
Dn Slope=0.005
Boundary for River Rch & Prof#=HICKORY33,Reach-1,7
Up Type=0
Dn Type=3
Dn Slope=0.005

--- HICKORY33.g01 (geometry) ---

Geom Title=Existing Conditions

River Reach=HICKORY33,Reach-1
Reach XY= 30
      2773198.50     10191369.00      2772299.50     10191541.00
      2772130.75     10191494.00      2771858.50     10191279.00
      2771499.25     10191258.00      2770999.50     10190678.00
      2770637.00     10190972.00      2770078.75     10191183.00
      2769693.25     10191083.00      2769107.00     10191519.00
      2769007.50     10191523.00      2768964.00     10191371.00
      2768562.00     10191430.00      2768490.25     10191623.00
      2768574.50     10191731.00      2768212.75     10191848.00
      2768222.50     10192050.00      2767732.50     10192044.00
      2767928.75     10192613.00      2767410.00     10192750.00
      2767188.00     10193275.00      2766591.25     10193475.00
      2766271.50     10193441.00      2766095.00     10193631.00
      2765459.50     10193474.00      2765139.75     10194047.00
      2764936.75     10194002.00      2764476.75     10194344.00
      2764280.25     10194825.00      2764037.00     10195118.00

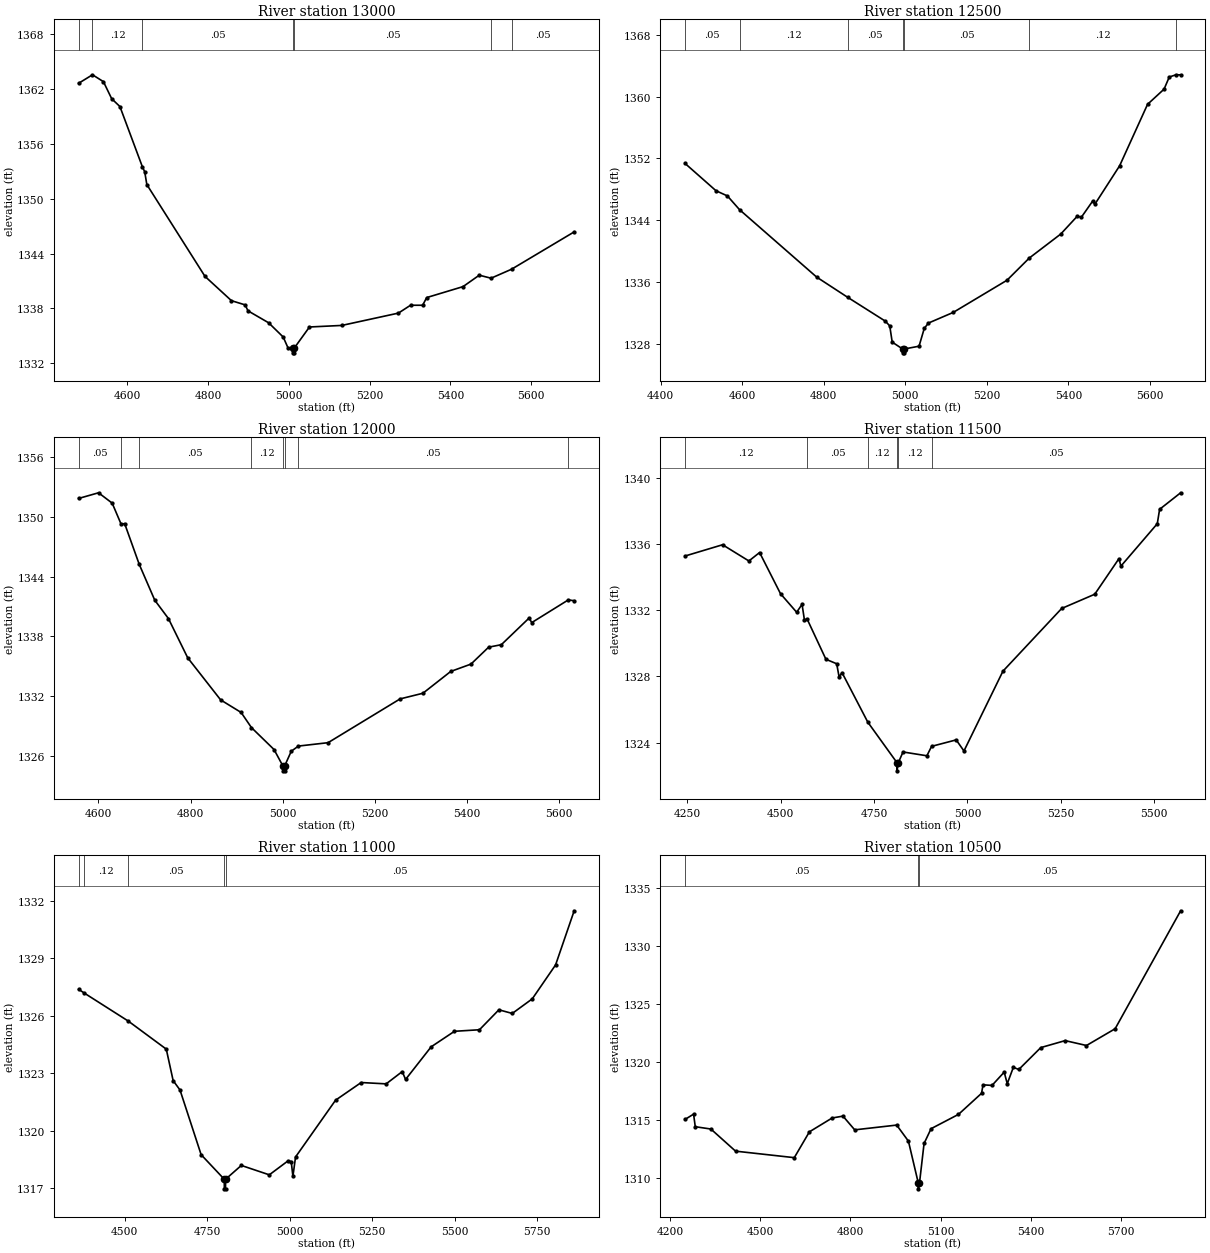
Type RM Length L Ch R = 1,13000,500,500,500
BEGIN DESCRIPTION:
HICKORY33 26.0
END DESCRIPTION:
XS GIS Cut Line= 3
      2772905.68     10190903.12      2772797.87     10191412.12
      2772778.62     10192117.96
#Sta/Elev= 30
  4479.7 1362.65  4514.0 1363.58  4541.0 1362.83  4561.5 1360.96  4581.9 1360.10
  4637.7 1353.48  4643.2 1352.97  4648.5 1351.56  4792.4 1341.51  4857.9 1338.85
  4891.8 1338.39  4898.8 1337.74  4949.9 1336.43  4986.0 1334.87  4997.9 1333.68
  5009.0 1333.64  5009.2 1333.14  5012.7 1333.14  5013.0 1333.64  5051.0 1335.97
  5131.0 1336.14  5271.1 1337.49  5301.1 1338.35  5331.1 1338.35  5341.1 1339.19
  5431.1 1340.39  5471.2 1341.64  5500.4 1341.31  5551.0 1342.29  5706.1 1346.38
#Mann=7,-1,0
  4479.7    0.05       0  4514.0    0.12       0  4637.7    0.05       0
  5009.0    0.05       0  5013.0    0.05       0  5500.4    0.12       0
  5551.0    0.05       0
Bank Sta=5009,5013
Exp/Cntr=0.3,0.1

Type RM Length L Ch R = 1,12500,500,500,500
BEGIN DESCRIPTION:
HICKORY33 25.0
END DESCRIPTION:
XS GIS Cut Line= 3
      2772555.67     10191053.13      2772316.63     10191537.23
      2772205.68     10192203.15
#Sta/Elev= 30
  4460.1 1351.34  4535.8 1347.81  4563.9 1347.13  4593.6 1345.35  4782.7 1336.61
  4858.4 1334.00  4951.0 1330.90  4961.9 1330.28  4967.9 1328.18  4993.4 1327.29
  4993.7 1326.79  4997.2 1326.79  4997.4 1327.29  5033.7 1327.65  5046.5 1329.96
  5056.7 1330.65  5117.5 1332.03  5249.3 1336.20  5304.0 1339.08  5381.1 1342.19
  5421.6 1344.50  5431.8 1344.38  5459.6 1346.48  5464.7 1346.05  5525.5 1351.04
  5594.0 1359.01  5634.5 1360.98  5647.2 1362.55  5663.7 1362.84  5675.1 1362.83
#Mann=7,-1,0
  4460.1    0.05       0  4593.6    0.12       0  4858.4    0.05       0
  4993.4    0.05       0  4997.4    0.05       0  5304.0    0.12       0
  5663.7    0.05       0
Bank Sta=4993.4,4997.4
Exp/Cntr=0.3,0.1

Type RM Length L Ch R = 1,12000,500,500,500
BEGIN DESCRIPTION:
HICKORY33 24.0
END DESCRIPTION:
XS GIS Cut Line= 3
      2772155.70     10190953.09      2771901.82     10191316.00
      2771605.02     10191874.89
#Sta/Elev= 30
  4557.1 1351.85  4600.3 1352.42  4629.9 1351.38  4649.3 1349.27  4657.0 1349.32
  4688.7 1345.22  4722.4 1341.62  4752.0 1339.78  4793.9 1335.83  4865.4 1331.60
  4909.8 1330.34  4932.2 1328.82  4981.3 1326.61  5000.4 1324.97  5000.7 1324.47
  5004.2 1324.47  5004.4 1324.97  5018.7 1326.44  5034.2 1326.96  5098.6 1327.30
  5254.9 1331.70  5304.5 1332.27  5364.8 1334.46  5408.8 1335.20  5447.1 1336.90
  5474.7 1337.15  5535.0 1339.83  5540.7 1339.37  5620.0 1341.65  5632.8 1341.57
#Mann=8,-1,0
  4557.1    0.05       0  4649.3    0.12       0  4688.7    0.05       0
  4932.2    0.12       0  5000.4    0.07       0  5004.4    0.12       0
  5034.2    0.05       0  5620.0    0.12       0
Bank Sta=5000.4,5004.4
Exp/Cntr=0.3,0.1

Type RM Length L Ch R = 1,11500,500,500,500
BEGIN DESCRIPTION:
HICKORY33 23.0
END DESCRIPTION:
XS GIS Cut Line= 3
      2771917.54     10190624.87      2771442.47     10191212.44
      2771271.67     10191756.87
#Sta/Elev= 30
  4244.4 1335.28  4344.7 1335.96  4415.1 1334.98  4443.8 1335.49  4499.8 1333.00
  4543.0 1331.88  4557.4 1332.36  4563.8 1331.41  4570.8 1331.48  4621.3 1329.04
  4650.1 1328.77  4656.5 1327.98  4664.5 1328.23  4733.4 1325.24  4811.2 1322.80
  4811.4 1322.30  4815.2 1322.80  4827.6 1323.44  4891.5 1323.21  4904.1 1323.78
  4969.9 1324.17  4990.7 1323.50  5095.0 1328.32  5252.2 1332.11  5340.7 1332.97
  5405.5 1335.12  5410.8 1334.67  5508.1 1337.23  5514.3 1338.10  5570.6 1339.10
#Mann=6,-1,0
  4244.4    0.12       0  4570.8    0.05       0  4733.4    0.12       0
  4811.2    0.05       0  4815.2    0.12       0  4904.1    0.05       0
Bank Sta=4811.2,4815.2
Exp/Cntr=0.3,0.1

Type RM Length L Ch R = 1,11000,500,500,500
BEGIN DESCRIPTION:
HICKORY33 22.0
END DESCRIPTION:
XS GIS Cut Line= 3
      2771570.28     10190305.48      2771171.69     10190805.06
      2771049.57     10191658.87
#Sta/Elev= 30
  4360.9 1327.38  4377.2 1327.19  4511.5 1325.72  4626.5 1324.26  4647.3 1322.62
  4668.1 1322.13  4732.1 1318.76  4802.2 1317.48  4802.5 1316.98  4806.0 1316.98
  4806.2 1317.48  4853.9 1318.20  4938.7 1317.71  4995.6 1318.44  5005.1 1318.40
  5010.2 1317.63  5018.2 1318.64  5139.5 1321.60  5217.1 1322.52  5292.8 1322.45
  5341.5 1323.09  5351.6 1322.68  5429.1 1324.38  5499.8 1325.19  5575.5 1325.27
  5634.4 1326.31  5674.9 1326.12  5735.5 1326.88  5806.2 1328.65  5862.5 1331.47
#Mann=5,-1,0
  4360.9    0.05       0  4377.2    0.12       0  4511.5    0.05       0
  4802.2    0.05       0  4806.2    0.05       0
Bank Sta=4802.2,4806.2
Exp/Cntr=0.3,0.1

Type RM Length L Ch R = 1,10500,500,500,500
BEGIN DESCRIPTION:
HICKORY33 21.0
END DESCRIPTION:
XS GIS Cut Line= 3
      2770466.15     10190166.61      2770803.30     10190836.00
      2770945.29     10191722.10
#Sta/Elev= 30
  4250.5 1315.08  4278.7 1315.53  4284.3 1314.45  4336.2 1314.25  4418.2 1312.35
  4613.4 1311.79  4663.6 1314.01  4739.2 1315.20  4775.2 1315.36  4814.2 1314.18
  4953.7 1314.59  4992.7 1313.21  5025.5 1309.61  5025.7 1309.11  5029.5 1309.61
  5044.7 1313.01  5068.0 1314.28  5159.1 1315.51  5235.7 1317.32  5240.7 1318.05
  5270.5 1318.00  5311.0 1319.14  5321.2 1318.15  5341.4 1319.55  5359.6 1319.37
  5432.6 1321.25  5513.6 1321.85  5584.5 1321.43  5679.7 1322.87  5897.4 1333.01
#Mann=3,-1,0
  4250.5    0.05       0  5025.5    0.05       0  5029.5    0.05       0
Bank Sta=5025.5,5029.5
Exp/Cntr=0.3,0.1

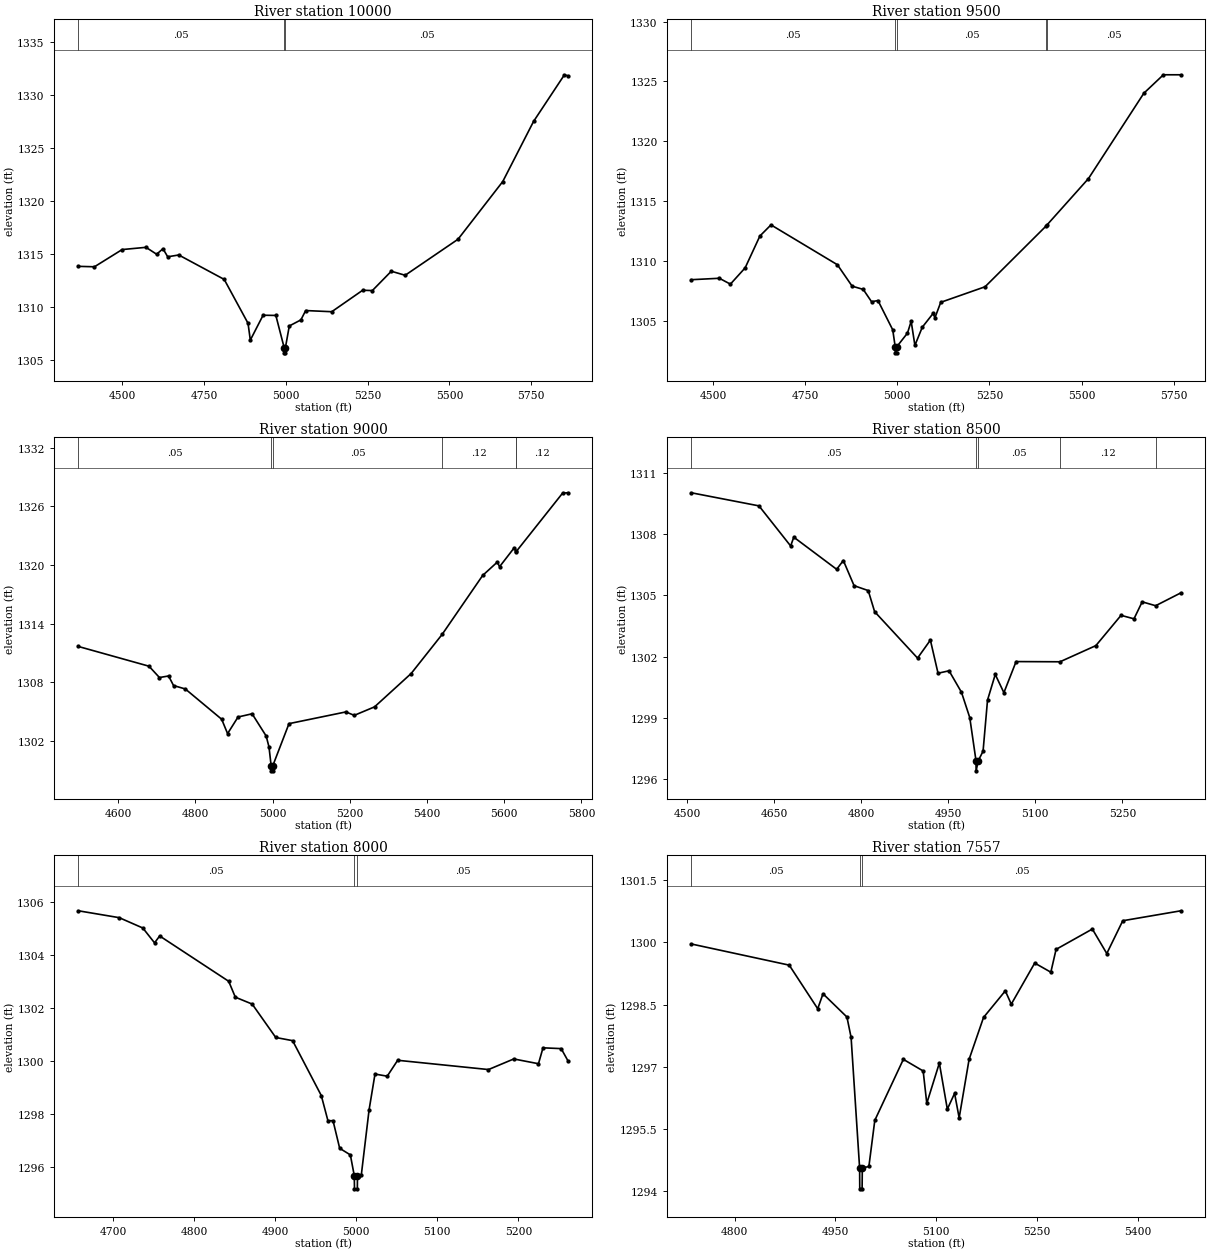
Type RM Length L Ch R = 1,10000,500,500,500
BEGIN DESCRIPTION:
HICKORY33 20.0
END DESCRIPTION:
XS GIS Cut Line= 3
      2770216.13     10190444.36      2770389.91     10191053.98
      2770848.06     10191784.62
#Sta/Elev= 30
  4366.1 1313.86  4415.4 1313.82  4500.0 1315.44  4572.8 1315.65  4605.4 1315.00
  4624.8 1315.52  4639.2 1314.76  4673.0 1314.93  4811.9 1312.63  4884.7 1308.50
  4891.7 1306.92  4930.7 1309.26  4969.7 1309.24  4995.0 1306.22  4995.2 1305.72
  4998.7 1305.72  4999.0 1306.22  5010.8 1308.25  5046.2 1308.82  5060.9 1309.70
  5140.6 1309.59  5235.0 1311.61  5264.6 1311.58  5322.5 1313.40  5364.9 1313.02
  5526.4 1316.41  5663.1 1321.84  5757.3 1327.50  5851.6 1331.89  5862.4 1331.79
#Mann=3,-1,0
  4366.1    0.05       0  4995.0    0.05       0  4999.0    0.05       0
Bank Sta=4995,4999
Exp/Cntr=0.3,0.1

Type RM Length L Ch R = 1,9500,500,500,500
BEGIN DESCRIPTION:
HICKORY33 19.0
END DESCRIPTION:
XS GIS Cut Line= 3
      2769917.52     10190597.18      2769944.13     10191155.64
      2769993.90     10191923.53
#Sta/Elev= 30
  4440.9 1308.44  4516.9 1308.56  4547.0 1308.07  4587.0 1309.43  4627.0 1312.09
  4657.1 1313.02  4837.3 1309.69  4877.3 1307.90  4907.4 1307.63  4930.0 1306.60
  4947.4 1306.70  4987.5 1304.25  4994.2 1302.83  4994.5 1302.33  4998.0 1302.33
  4998.2 1302.83  5027.5 1303.98  5037.5 1304.97  5047.6 1302.95  5067.6 1304.47
  5097.0 1305.62  5102.0 1305.26  5117.7 1306.55  5238.0 1307.85  5404.4 1312.95
  5406.2 1313.02  5518.6 1316.89  5668.9 1324.02  5721.9 1325.56  5769.5 1325.56
#Mann=5,-1,0
  4440.9    0.05       0  4994.2    0.05       0  4998.2    0.05       0
  5404.4    0.12       0  5406.2    0.05       0
Bank Sta=4994.2,4998.2
Exp/Cntr=0.3,0.1

Type RM Length L Ch R = 1,9000,500,500,500
BEGIN DESCRIPTION:
HICKORY33 18.0
END DESCRIPTION:
XS GIS Cut Line= 3
      2769271.67     10190805.45      2769540.29     10191230.95
      2769905.70     10191903.15
#Sta/Elev= 30
  4496.8 1311.67  4679.8 1309.65  4706.9 1308.49  4730.6 1308.65  4743.4 1307.67
  4773.9 1307.32  4868.1 1304.22  4883.4 1302.75  4910.5 1304.45  4946.9 1304.78
  4983.4 1302.50  4990.7 1301.38  4996.3 1299.44  4996.6 1298.94  5000.1 1298.94
  5000.3 1299.44  5042.5 1303.77  5189.8 1304.97  5211.6 1304.62  5264.2 1305.49
  5358.9 1308.90  5439.3 1312.91  5544.2 1318.94  5582.2 1320.31  5587.9 1319.83
  5625.9 1321.77  5630.7 1321.40  5631.0 1321.38  5751.3 1327.37  5765.1 1327.40
#Mann=6,-1,0
  4496.8    0.05       0  4996.3    0.05       0  5000.3    0.05       0
  5439.3    0.12       0  5630.7    0.05       0  5631.0    0.12       0
Bank Sta=4996.3,5000.3
Exp/Cntr=0.3,0.1

Type RM Length L Ch R = 1,8500,500,500,500
BEGIN DESCRIPTION:
HICKORY33 17.0
END DESCRIPTION:
XS GIS Cut Line= 3
      2768959.18     10191048.51      2769135.95     10191508.51
      2769334.02     10191798.29
#Sta/Elev= 30
  4507.2 1310.01  4623.8 1309.37  4678.4 1307.41  4683.8 1307.84  4757.7 1306.27
  4769.2 1306.70  4787.7 1305.47  4812.1 1305.23  4823.1 1304.20  4897.1 1301.93
  4919.2 1302.81  4932.4 1301.19  4951.4 1301.31  4972.8 1300.26  4987.1 1299.02
  4997.8 1296.92  4998.0 1296.42  5001.8 1296.92  5010.0 1297.38  5017.7 1299.88
  5031.0 1301.13  5045.9 1300.24  5066.9 1301.76  5142.6 1301.75  5204.4 1302.54
  5247.8 1304.02  5270.1 1303.85  5284.2 1304.68  5307.4 1304.49  5351.0 1305.12
#Mann=5,-1,0
  4507.2    0.05       0  4997.8    0.03       0  5001.8    0.05       0
  5142.6    0.12       0  5307.4    0.05       0
Bank Sta=4997.8,5001.8
Exp/Cntr=0.3,0.1

Type RM Length L Ch R = 1,8000,443,443,443
BEGIN DESCRIPTION:
HICKORY33 16.0
END DESCRIPTION:
XS GIS Cut Line= 3
      2768581.10     10191146.50      2768789.74     10191419.00
      2768905.66     10191653.07
#Sta/Elev= 30
  4656.8 1305.67  4707.3 1305.41  4736.4 1305.02  4750.9 1304.46  4757.2 1304.72
  4842.4 1303.01  4850.6 1302.41  4871.4 1302.15  4900.5 1300.89  4921.3 1300.77
  4956.7 1298.70  4964.9 1297.75  4971.2 1297.75  4979.4 1296.71  4992.6 1296.46
  4997.4 1295.68  4997.7 1295.18  5001.2 1295.18  5001.4 1295.68  5006.1 1295.70
  5015.7 1298.16  5023.0 1299.51  5038.1 1299.43  5051.0 1300.03  5163.1 1299.68
  5194.3 1300.08  5224.8 1299.90  5230.4 1300.50  5252.8 1300.47  5261.2 1300.01
#Mann=3,-1,0
  4656.8    0.05       0  4997.4    0.05       0  5001.4    0.05       0
Bank Sta=4997.4,5001.4
Exp/Cntr=0.3,0.1

Type RM Length L Ch R = 1,7557,520,520,520
BEGIN DESCRIPTION:
HICKORY33 15.0
END DESCRIPTION:
XS GIS Cut Line= 3
      2768282.95     10191452.49      2768497.50     10191607.00
      2768927.92     10191781.91
#Sta/Elev= 30
  4735.6 1299.96  4881.4 1299.45  4923.8 1298.40  4931.7 1298.76  4967.3 1298.20
  4973.5 1297.71  4986.2 1294.56  4986.4 1294.06  4989.9 1294.06  4990.2 1294.56
  5000.0 1294.60  5008.8 1295.71  5051.3 1297.18  5080.8 1296.90  5086.2 1296.12
  5104.9 1297.09  5116.8 1295.98  5127.6 1296.36  5134.4 1295.77  5149.2 1297.18
  5170.7 1298.19  5203.1 1298.83  5212.0 1298.51  5246.9 1299.50  5270.9 1299.28
  5278.7 1299.83  5332.7 1300.32  5354.2 1299.73  5378.0 1300.52  5464.6 1300.76
#Mann=3,-1,0
  4735.6    0.05       0  4986.2    0.05       0  4990.2    0.05       0
Bank Sta=4986.2,4990.2
Exp/Cntr=0.3,0.1

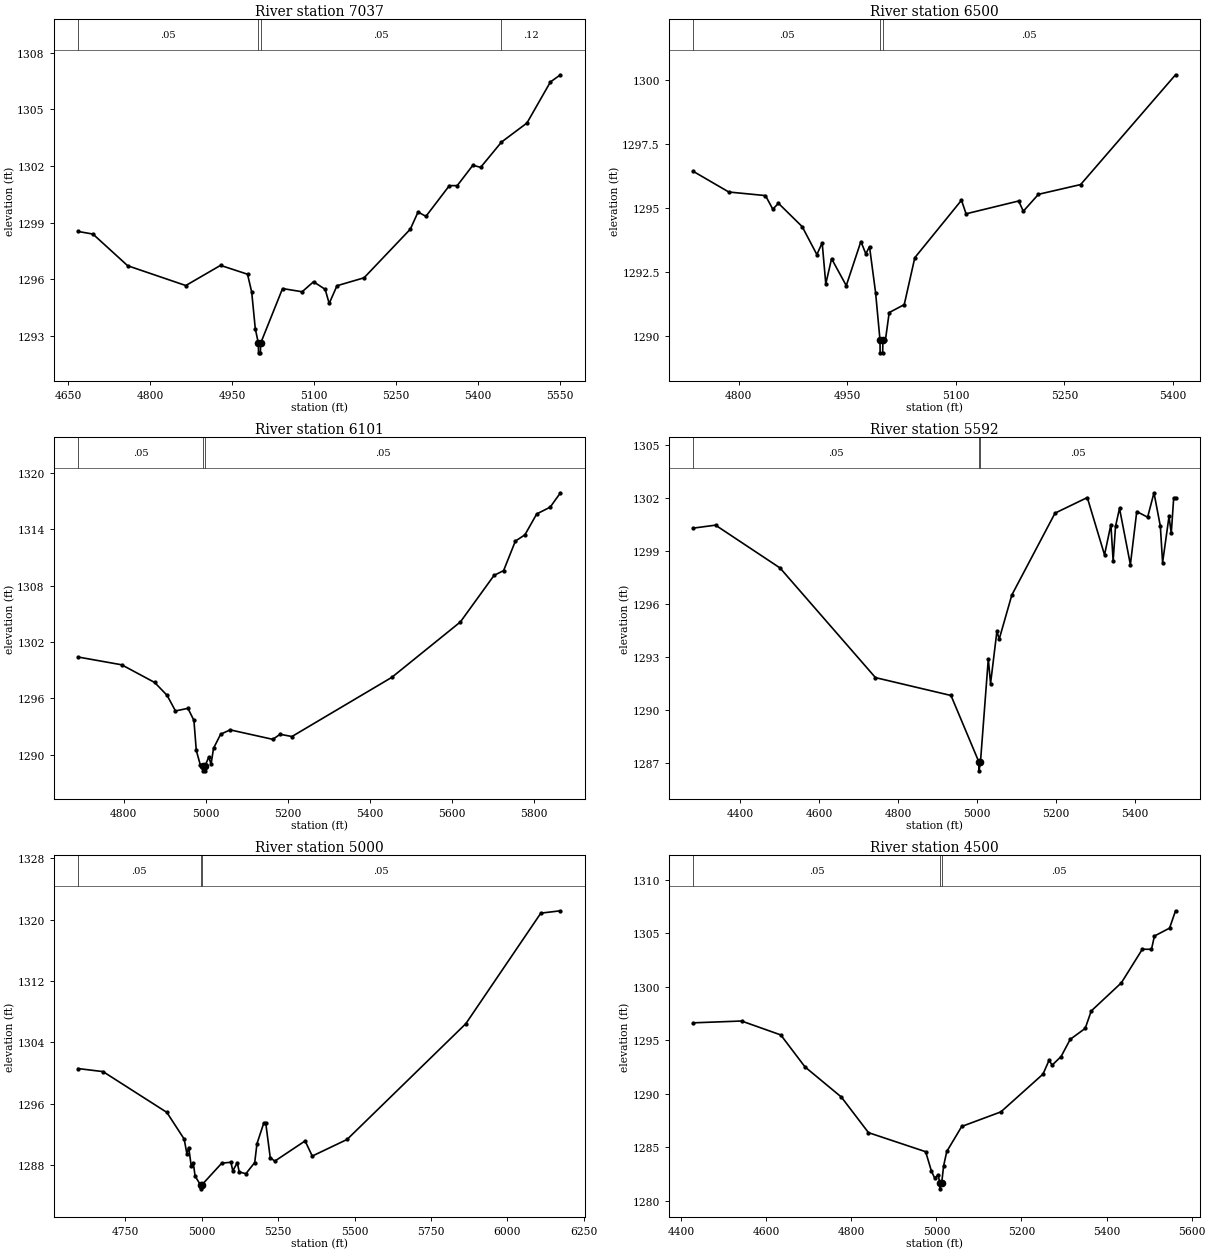
Type RM Length L Ch R = 1,7037,537,537,537
BEGIN DESCRIPTION:
HICKORY33 14.0
END DESCRIPTION:
XS GIS Cut Line= 3
      2768040.78     10191569.69      2768270.50     10191834.95
      2768610.56     10192244.60
#Sta/Elev= 30
  4667.7 1298.53  4695.1 1298.39  4758.7 1296.71  4865.1 1295.66  4928.7 1296.73
  4978.1 1296.26  4985.7 1295.32  4992.3 1293.37  4998.0 1292.59  4998.2 1292.09
  5001.7 1292.09  5002.0 1292.59  5042.2 1295.50  5078.1 1295.33  5098.9 1295.86
  5120.2 1295.46  5127.6 1294.71  5141.9 1295.65  5191.4 1296.07  5276.1 1298.65
  5290.3 1299.56  5304.7 1299.33  5347.6 1300.96  5362.0 1300.96  5390.6 1302.04
  5404.9 1301.93  5443.0 1303.27  5489.6 1304.28  5532.6 1306.46  5551.0 1306.84
#Mann=4,-1,0
  4667.7    0.05       0  4998.0    0.05       0  5002.0    0.05       0
  5443.0    0.12       0
Bank Sta=4998,5002
Exp/Cntr=0.3,0.1

Type RM Length L Ch R = 1,6500,399,399,399
BEGIN DESCRIPTION:
HICKORY33 13.0
END DESCRIPTION:
XS GIS Cut Line= 3
      2767950.54     10191744.42      2767994.48     10192003.93
      2768236.97     10192326.31
#Sta/Elev= 30
  4736.8 1296.43  4786.2 1295.62  4836.9 1295.48  4847.0 1294.95  4854.8 1295.18
  4887.6 1294.27  4907.9 1293.18  4915.2 1293.64  4920.2 1292.04  4928.2 1293.02
  4948.5 1291.97  4968.7 1293.69  4975.5 1293.21  4980.6 1293.49  4989.0 1291.70
  4995.1 1289.85  4995.3 1289.35  4998.8 1289.35  4999.1 1289.85  5002.6 1289.85
  5007.8 1290.92  5028.6 1291.23  5043.2 1293.06  5107.7 1295.30  5114.0 1294.77
  5186.7 1295.27  5193.1 1294.87  5214.0 1295.53  5272.3 1295.91  5403.4 1300.19
#Mann=3,-1,0
  4736.8    0.05       0  4995.1    0.05       0  4999.1    0.05       0
Bank Sta=4995.1,4999.1
Exp/Cntr=0.3,0.1

Type RM Length L Ch R = 1,6101,509,509,509
BEGIN DESCRIPTION:
HICKORY33 12.0
END DESCRIPTION:
XS GIS Cut Line= 3
      2767431.42     10192111.02      2767738.25     10192163.00
      2768528.60     10192513.79
#Sta/Elev= 30
  4688.8 1300.41  4795.4 1299.58  4875.7 1297.70  4906.0 1296.33  4926.4 1294.67
  4956.8 1294.95  4971.4 1293.66  4977.1 1290.48  4987.3 1288.87  4994.2 1288.80
  4994.4 1288.30  4997.9 1288.30  4998.2 1288.80  5007.6 1289.77  5013.1 1288.99
  5019.1 1290.69  5036.4 1292.19  5059.6 1292.66  5163.6 1291.65  5181.4 1292.19
  5210.2 1291.95  5453.8 1298.25  5620.8 1304.14  5702.8 1309.09  5726.1 1309.60
  5754.8 1312.74  5778.1 1313.41  5806.8 1315.63  5839.6 1316.35  5864.7 1317.88
#Mann=3,-1,0
  4688.8    0.05       0  4994.2    0.05       0  4998.2    0.05       0
Bank Sta=4994.2,4998.2
Exp/Cntr=0.3,0.1

Type RM Length L Ch R = 1,5592,592,592,592
BEGIN DESCRIPTION:
HICKORY33 11.0
END DESCRIPTION:
XS GIS Cut Line= 3
      2767382.41     10192146.05      2767928.75     10192613.00
      2768368.86     10192854.05
#Sta/Elev= 30
  4281.3 1300.28  4338.2 1300.45  4501.3 1298.03  4742.8 1291.83  4933.8 1290.82
  5004.4 1287.06  5004.7 1286.56  5008.4 1287.06  5028.2 1292.89  5033.9 1291.49
  5050.0 1294.46  5055.7 1294.00  5087.7 1296.50  5197.0 1301.13  5278.6 1302.01
  5322.2 1298.77  5338.3 1300.48  5344.0 1298.43  5350.0 1300.38  5360.1 1301.40
  5387.6 1298.22  5403.7 1301.22  5431.2 1300.90  5447.3 1302.28  5463.4 1300.39
  5469.1 1298.33  5485.3 1300.94  5491.0 1299.99  5497.2 1302.00  5501.8 1302.00
#Mann=3,-1,0
  4281.3    0.05       0  5004.4    0.05       0  5008.4    0.05       0
Bank Sta=5004.4,5008.4
Exp/Cntr=0.3,0.1

Type RM Length L Ch R = 1,5000,500,500,500
BEGIN DESCRIPTION:
HICKORY33 10.0
END DESCRIPTION:
XS GIS Cut Line= 3
      2767155.38     10192458.57      2767386.28     10192791.05
      2768355.68     10193453.11
#Sta/Elev= 30
  4595.2 1300.59  4677.2 1300.19  4885.9 1294.88  4942.7 1291.40  4951.4 1289.52
  4957.5 1290.30  4966.0 1287.85  4972.4 1288.33  4978.4 1286.58  4996.2 1285.42
  4996.5 1284.92  5000.2 1285.42  5065.8 1288.27  5095.6 1288.38  5101.7 1287.27
  5116.6 1288.32  5122.7 1287.13  5144.6 1286.89  5173.5 1288.35  5180.9 1290.81
  5203.3 1293.51  5209.4 1293.54  5224.3 1288.98  5239.2 1288.53  5338.3 1291.16
  5361.8 1289.19  5475.6 1291.35  5864.4 1306.44  6109.6 1320.83  6173.9 1321.14
#Mann=3,-1,0
  4595.2    0.05       0  4996.2    0.05       0  5000.2    0.05       0
Bank Sta=4996.2,5000.2
Exp/Cntr=0.3,0.1

Type RM Length L Ch R = 1,4500,500,500,500
BEGIN DESCRIPTION:
HICKORY33 9.0
END DESCRIPTION:
XS GIS Cut Line= 3
      2766848.42     10192809.23      2767222.10     10193242.29
      2767605.71     10193653.14
#Sta/Elev= 30
  4428.0 1296.62  4542.0 1296.79  4634.2 1295.49  4691.2 1292.50  4776.5 1289.69
  4840.4 1286.36  4974.7 1284.58  4988.5 1282.75  4996.2 1282.10  5004.0 1282.44
  5008.3 1281.61  5008.5 1281.11  5012.3 1281.61  5017.1 1283.28  5024.4 1284.60
  5059.6 1286.94  5151.6 1288.30  5250.6 1291.83  5264.8 1293.12  5272.1 1292.67
  5293.1 1293.47  5314.6 1295.08  5349.8 1296.10  5364.0 1297.73  5434.8 1300.36
  5484.1 1303.50  5505.6 1303.49  5512.5 1304.73  5548.1 1305.47  5562.1 1307.09
#Mann=3,-1,0
  4428.0    0.05       0  5008.3    0.05       0  5012.3    0.05       0
Bank Sta=5008.3,5012.3
Exp/Cntr=0.3,0.1

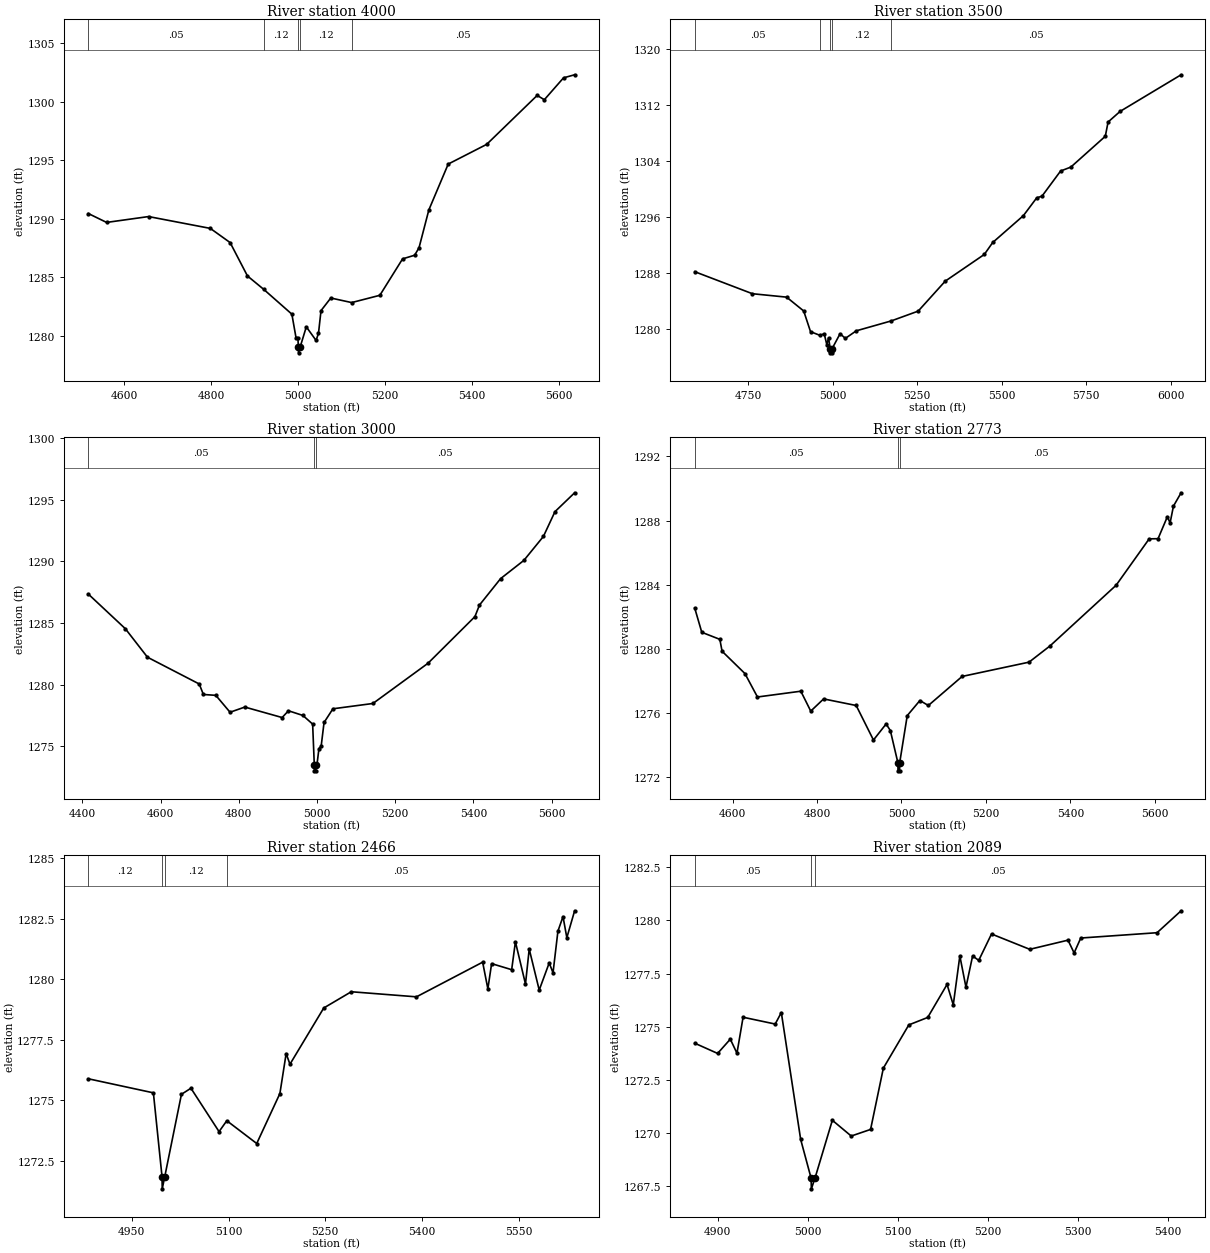
Type RM Length L Ch R = 1,4000,500,500,500
BEGIN DESCRIPTION:
HICKORY33 8.0
END DESCRIPTION:
XS GIS Cut Line= 3
      2766542.50     10192930.44      2766748.83     10193365.93
      2767042.54     10193930.50
#Sta/Elev= 30
  4518.1 1290.45  4560.2 1289.69  4656.7 1290.19  4798.7 1289.18  4844.2 1287.97
  4884.1 1285.12  4921.1 1283.99  4986.2 1281.86  4995.7 1279.86  5000.0 1279.86
  5001.2 1279.06  5001.5 1278.56  5005.3 1279.06  5019.4 1280.78  5041.8 1279.62
  5047.4 1280.22  5053.2 1282.16  5075.7 1283.24  5123.7 1282.85  5188.5 1283.47
  5240.8 1286.58  5268.5 1286.89  5278.6 1287.53  5301.2 1290.76  5345.7 1294.67
  5434.1 1296.35  5550.3 1300.53  5566.7 1300.16  5610.9 1302.03  5636.4 1302.29
#Mann=5,-1,0
  4518.1    0.05       0  4921.1    0.12       0  5001.2    0.07       0
  5005.3    0.12       0  5123.7    0.05       0
Bank Sta=5001.2,5005.3
Exp/Cntr=0.3,0.1

Type RM Length L Ch R = 1,3500,500,500,500
BEGIN DESCRIPTION:
HICKORY33 7.0
END DESCRIPTION:
XS GIS Cut Line= 3
      2766230.01     10193034.58      2766292.96     10193438.00
      2766655.68     10194403.09
#Sta/Elev= 30
  4591.7 1288.13  4762.3 1284.98  4863.5 1284.49  4914.1 1282.51  4934.3 1279.55
  4962.4 1279.02  4974.8 1279.25  4982.5 1277.69  4987.6 1278.66  4992.9 1277.02
  4993.2 1276.52  4996.8 1276.52  4997.1 1277.02  5021.7 1279.25  5037.5 1278.59
  5069.6 1279.67  5173.3 1281.09  5252.9 1282.49  5333.0 1286.78  5448.6 1290.60
  5473.5 1292.31  5564.2 1296.15  5603.7 1298.70  5619.3 1298.94  5674.4 1302.54
  5704.7 1303.10  5806.7 1307.51  5814.9 1309.55  5850.5 1311.07  6031.0 1316.31
#Mann=5,-1,0
  4591.7    0.05       0  4962.4    0.12       0  4992.9    0.07       0
  4997.1    0.12       0  5173.3    0.05       0
Bank Sta=4992.9,4997.1
Exp/Cntr=0.3,0.1

Type RM Length L Ch R = 1,3000,227,227,227
BEGIN DESCRIPTION:
HICKORY33 6.0
END DESCRIPTION:
XS GIS Cut Line= 3
      2766091.11     10193055.49      2765896.47     10193607.16
      2766209.16     10194187.37
#Sta/Elev= 30
  4415.0 1287.34  4509.8 1284.53  4566.4 1282.22  4698.8 1280.05  4709.4 1279.20
  4741.2 1279.13  4777.6 1277.76  4815.4 1278.18  4910.9 1277.33  4927.0 1277.88
  4963.9 1277.50  4988.9 1276.80  4993.1 1273.51  4993.4 1273.01  4997.1 1273.01
  4997.3 1273.51  5000.0 1273.51  5005.0 1274.81  5010.7 1275.01  5018.1 1276.93
  5040.8 1278.04  5143.1 1278.47  5284.0 1281.73  5404.0 1285.51  5415.7 1286.45
  5469.7 1288.59  5529.3 1290.07  5579.2 1292.01  5608.8 1294.02  5659.1 1295.55
#Mann=3,-1,0
  4415.0    0.05       0  4993.1    0.05       0  4997.3    0.05       0
Bank Sta=4993.1,4997.3
Exp/Cntr=0.3,0.1

Type RM Length L Ch R = 1,2773,307,307,307
BEGIN DESCRIPTION:
Mapping XS 403f031f
END DESCRIPTION:
XS GIS Cut Line= 4
      2765834.45     10193087.72      2765688.60     10193455.81
      2765688.60     10193782.20      2765959.42     10194115.52
#Sta/Elev= 30
  4510.5 1282.54  4527.1 1281.04  4569.9 1280.60  4575.2 1279.86  4629.3 1278.47
  4659.0 1277.01  4761.7 1277.37  4785.2 1276.13  4815.7 1276.89  4892.8 1276.48
  4933.7 1274.33  4963.7 1275.33  4973.7 1274.92  4991.6 1272.91  4991.9 1272.41
  4995.6 1272.41  4995.8 1272.91  5013.7 1275.85  5043.7 1276.79  5063.7 1276.48
  5143.7 1278.29  5302.2 1279.18  5351.8 1280.19  5508.4 1283.97  5586.7 1286.86
  5607.7 1286.87  5629.8 1288.24  5636.2 1287.85  5644.2 1288.90  5662.3 1289.73
#Mann=3,-1,0
  4510.5    0.05       0  4991.6    0.03       0  4995.8    0.05       0
Bank Sta=4991.6,4995.8
Exp/Cntr=0.3,0.1

Type RM Length L Ch R = 1,2466,377,377,377
BEGIN DESCRIPTION:
Mapping XS 1ada271b
END DESCRIPTION:
XS GIS Cut Line= 2
      2765390.00     10193379.44      2765778.90     10194025.29
#Sta/Elev= 30
  4882.6 1275.89  4983.5 1275.31  4996.9 1271.85  4997.2 1271.35  5001.1 1271.85
  5027.0 1275.25  5041.7 1275.50  5085.3 1273.71  5097.3 1274.16  5143.7 1273.22
  5179.6 1275.28  5189.3 1276.93  5195.2 1276.49  5247.6 1278.81  5290.3 1279.48
  5391.3 1279.27  5493.9 1280.70  5502.0 1279.60  5507.8 1280.64  5538.9 1280.39
  5544.7 1281.54  5560.3 1279.80  5566.1 1281.24  5581.6 1279.55  5597.1 1280.67
  5603.0 1280.26  5610.6 1281.98  5618.5 1282.58  5624.4 1281.71  5636.5 1282.82
#Mann=4,-1,0
  4882.6    0.12       0  4996.9    0.07       0  5001.1    0.12       0
  5097.3    0.05       0
Bank Sta=4996.9,5001.1
Exp/Cntr=0.3,0.1

Type RM Length L Ch R = 1,2089,199,199,199
BEGIN DESCRIPTION:
Mapping XS 516d2ac1
END DESCRIPTION:
XS GIS Cut Line= 2
      2765209.43     10193643.31      2765605.26     10194011.36
#Sta/Elev= 30
  4874.6 1274.23  4900.0 1273.75  4914.1 1274.42  4921.5 1273.76  4928.3 1275.45
  4964.0 1275.13  4970.8 1275.67  4992.3 1269.71  5003.9 1267.89  5004.2 1267.39
  5008.2 1267.89  5027.5 1270.61  5048.5 1269.87  5070.0 1270.18  5084.2 1273.06
  5112.5 1275.09  5133.5 1275.44  5155.0 1276.99  5161.9 1276.03  5169.2 1278.33
  5176.0 1276.86  5183.4 1278.33  5190.2 1278.12  5204.4 1279.36  5246.9 1278.64
  5289.4 1279.07  5296.2 1278.47  5303.6 1279.17  5388.4 1279.42  5415.1 1280.45
#Mann=3,-1,0
  4874.6    0.05       0  5003.9    0.03       0  5008.2    0.05       0
Bank Sta=5003.9,5008.2
Exp/Cntr=0.3,0.1

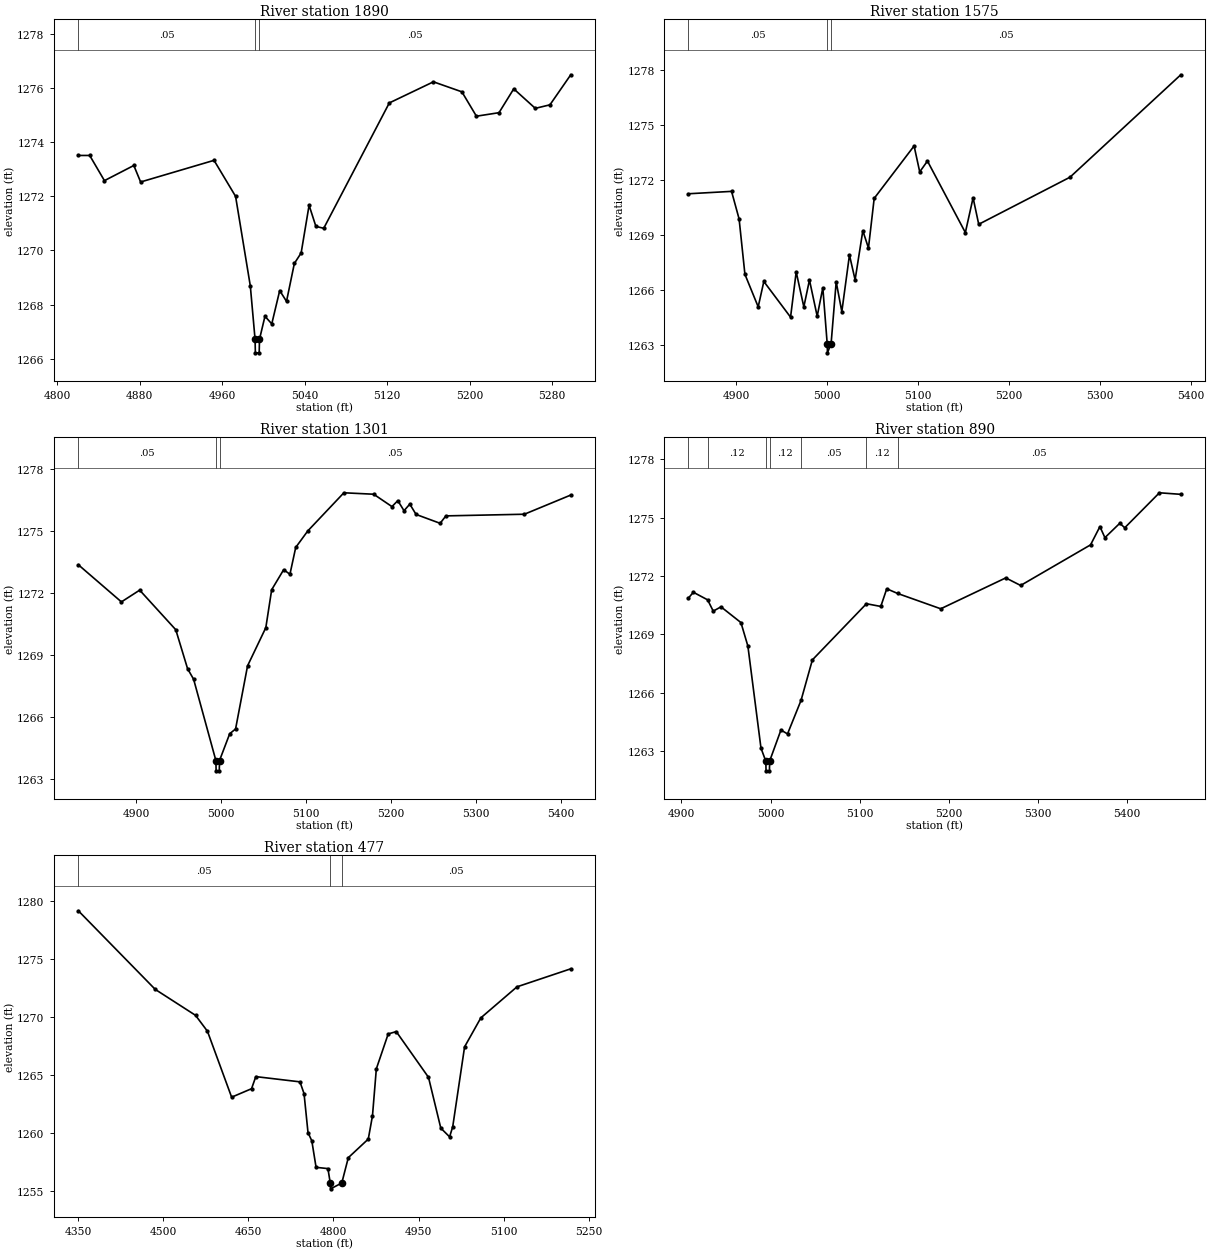
Type RM Length L Ch R = 1,1890,315,315,315
BEGIN DESCRIPTION:
Mapping XS 53f6cb74
END DESCRIPTION:
XS GIS Cut Line= 2
      2765084.42     10193789.14      2765445.57     10194101.67
#Sta/Elev= 30
  4820.5 1273.51  4831.5 1273.51  4845.8 1272.58  4874.3 1273.14  4880.9 1272.53
  4952.1 1273.33  4973.0 1272.00  4987.3 1268.69  4991.9 1266.72  4992.2 1266.22
  4995.9 1266.22  4996.2 1266.72  5001.5 1267.57  5008.1 1267.29  5015.8 1268.52
  5022.4 1268.12  5030.0 1269.52  5036.6 1269.91  5044.3 1271.67  5050.9 1270.89
  5058.5 1270.82  5122.1 1275.45  5164.9 1276.23  5192.5 1275.86  5206.6 1274.96
  5228.5 1275.09  5242.8 1275.97  5263.7 1275.25  5277.9 1275.38  5298.1 1276.49
#Mann=3,-1,0
  4820.5    0.05       0  4991.9    0.03       0  4996.2    0.05       0
Bank Sta=4991.9,4996.2
Exp/Cntr=0.3,0.1

Type RM Length L Ch R = 1,1575,274,274,274
BEGIN DESCRIPTION:
Mapping XS 8569ebe5
END DESCRIPTION:
XS GIS Cut Line= 2
      2764903.90     10193928.06      2765223.34     10194365.55
#Sta/Elev= 30
  4847.1 1271.25  4894.6 1271.38  4902.9 1269.88  4909.3 1266.87  4923.9 1265.10
  4930.1 1266.48  4959.5 1264.54  4965.7 1267.00  4974.1 1265.10  4980.3 1266.56
  4988.8 1264.59  4995.0 1266.14  4999.8 1263.10  5000.1 1262.60  5004.1 1263.10
  5009.7 1266.46  5015.9 1264.84  5024.3 1267.92  5030.5 1266.57  5039.0 1269.24
  5045.2 1268.30  5051.5 1271.00  5095.4 1273.85  5101.6 1272.44  5110.1 1273.03
  5151.8 1269.14  5160.3 1271.03  5166.5 1269.59  5266.9 1272.15  5388.8 1277.72
#Mann=3,-1,0
  4847.1    0.05       0  4999.8    0.05       0  5004.1    0.05       0
Bank Sta=4999.8,5004.1
Exp/Cntr=0.3,0.1

Type RM Length L Ch R = 1,1301,411,411,411
BEGIN DESCRIPTION:
Mapping XS c00c1b62
END DESCRIPTION:
XS GIS Cut Line= 2
      2764681.69     10194025.29      2765105.25     10194421.08
#Sta/Elev= 30
  4832.1 1273.38  4882.8 1271.58  4904.3 1272.15  4946.8 1270.23  4960.7 1268.34
  4967.8 1267.83  4994.0 1263.89  4994.3 1263.39  4998.0 1263.39  4998.3 1263.89
  5010.3 1265.19  5017.2 1265.42  5031.3 1268.48  5052.8 1270.33  5059.7 1272.17
  5073.8 1273.14  5081.2 1272.92  5088.0 1274.22  5102.2 1275.02  5144.7 1276.87
  5179.8 1276.80  5201.3 1276.20  5208.2 1276.49  5215.5 1276.00  5222.3 1276.32
  5229.7 1275.82  5258.0 1275.39  5264.8 1275.75  5357.2 1275.83  5411.8 1276.76
#Mann=3,-1,0
  4832.1    0.05       0  4994.0    0.05       0  4998.3    0.05       0
Bank Sta=4994,4998.3
Exp/Cntr=0.3,0.1

Type RM Length L Ch R = 1,890,413,413,413
BEGIN DESCRIPTION:
Mapping XS e7615973
END DESCRIPTION:
XS GIS Cut Line= 2
      2764383.03     10194316.92      2764876.08     10194566.91
#Sta/Elev= 30
  4907.8 1270.86  4913.4 1271.16  4929.4 1270.77  4935.7 1270.19  4944.4 1270.41
  4966.8 1269.60  4974.6 1268.39  4989.3 1263.14  4994.7 1262.47  4995.0 1261.97
  4998.8 1261.97  4999.0 1262.47  5011.7 1264.07  5019.1 1263.87  5034.3 1265.60
  5047.0 1267.68  5107.7 1270.57  5123.8 1270.43  5130.5 1271.34  5142.6 1271.10
  5191.1 1270.31  5264.1 1271.90  5280.8 1271.51  5359.3 1273.60  5369.8 1274.54
  5375.4 1273.97  5392.1 1274.71  5397.7 1274.48  5436.6 1276.28  5460.6 1276.20
#Mann=7,-1,0
  4907.8    0.05       0  4929.4    0.12       0  4994.7    0.07       0
  4999.0    0.12       0  5034.3    0.05       0  5107.7    0.12       0
  5142.6    0.05       0
Bank Sta=4994.7,4999
Exp/Cntr=0.3,0.1

Type RM Length L Ch R = 1,477,0,0,0
BEGIN DESCRIPTION:
HICKORY33 2.0
END DESCRIPTION:
XS GIS Cut Line= 3
      2763839.12     10194308.30      2764323.50     10194741.00
      2764490.51     10194881.42
#Sta/Elev= 30
  4350.5 1279.13  4486.0 1272.37  4557.0 1270.14  4578.0 1268.77  4620.6 1263.10
  4655.7 1263.83  4663.2 1264.87  4741.0 1264.42  4748.2 1263.41  4755.2 1260.05
  4761.9 1259.35  4769.4 1257.07  4790.3 1256.96  4794.4 1255.72  4794.9 1255.22
  4814.7 1255.72  4826.2 1257.90  4861.4 1259.50  4868.8 1261.50  4875.6 1265.54
  4896.5 1268.54  4910.7 1268.74  4967.5 1264.81  4989.2 1260.44  5004.7 1259.69
  5010.2 1260.56  5031.1 1267.43  5059.7 1269.92  5123.4 1272.59  5218.2 1274.14
#Mann=3,-1,0
  4350.5    0.05       0  4794.4    0.05       0  4814.7    0.05       0
Bank Sta=4794.4,4814.7
Exp/Cntr=0.3,0.1

Chan Stop Cuts=-1