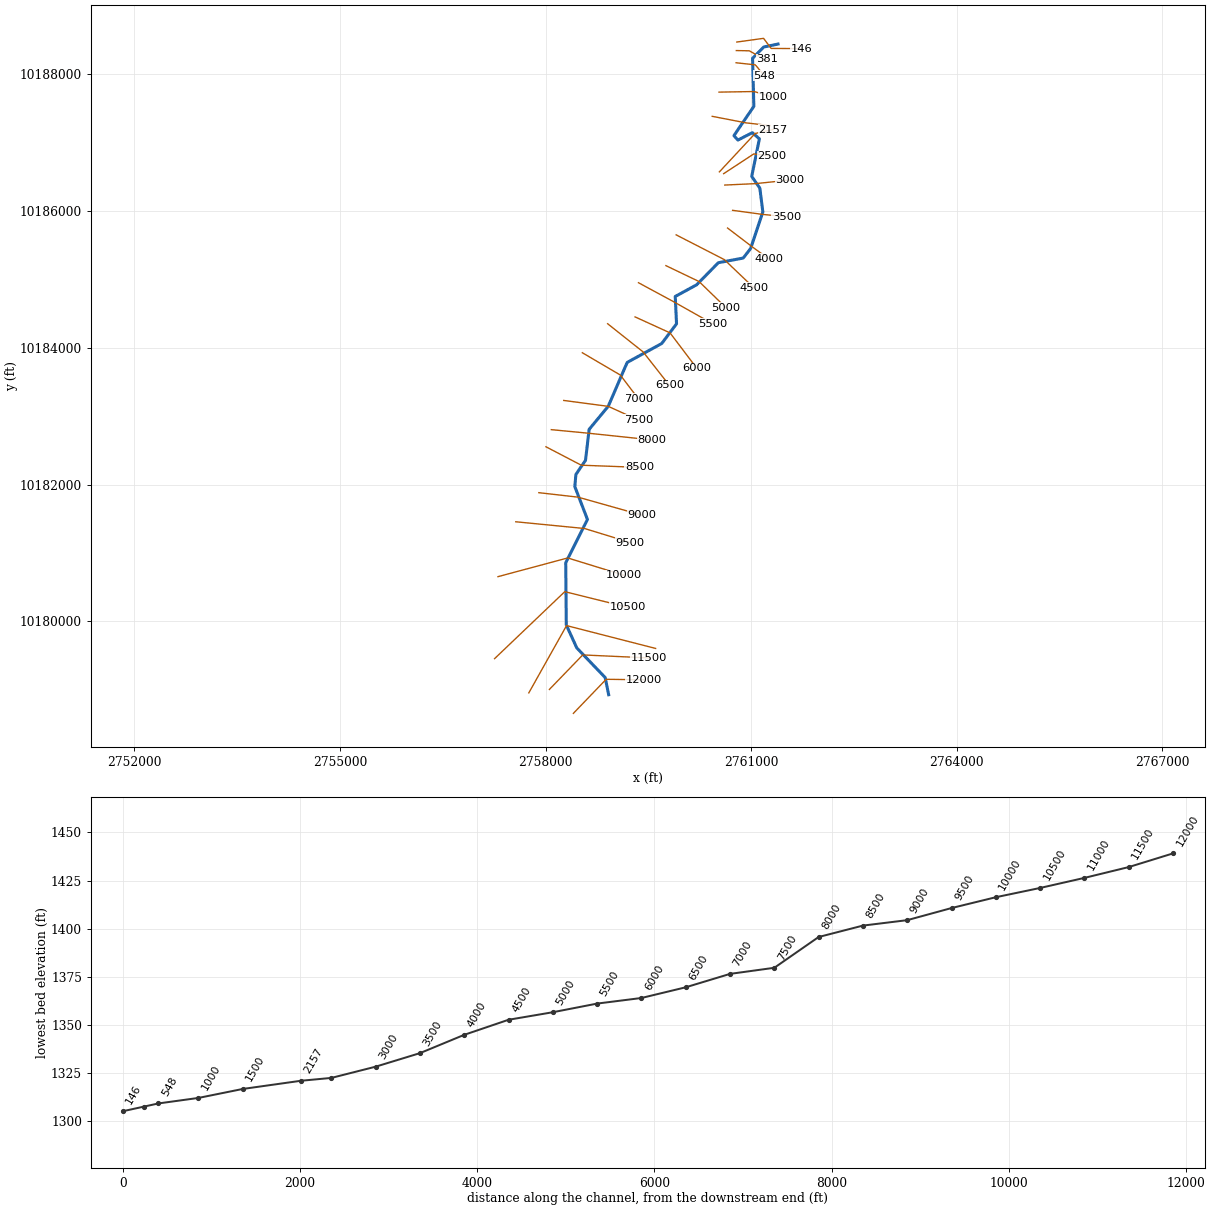
--- HICKORY34.prj (project) ---

Proj Title=HICKORY34 Base Level Engineering
Current Plan=p01
Default Exp/Contr=0.3,0.1
English Units
Geom File=g01
Flow File=f01
Plan File=p01
BEGIN DESCRIPTION:
HICKORY34
END DESCRIPTION:

--- HICKORY34.p01 (plan) ---

Plan Title=Multiple Run
Short Identifier=Multiple
Geom File=g01
Flow File=f01
Subcritical Flow
K Sum by GR= 0
Std Step Tol= 0.01
Critical Tol= 0.01
Num of Std Step Trials= 20
Max Error Tol= 0.3
Flow Tol Ratio= 0.001
Split Flow NTrial= 30
Split Flow Tol= 0.02
Split Flow Ratio= 0.02
Log Output Level= 0
Friction Slope Method= 1
Unsteady Friction Slope Method= 2
Unsteady Bridges Friction Slope Method= 1
Parabolic Critical Depth
Global Vel Dist=  1 , 1 , 1
Global Log Level= 0
CheckData=True
Encroach Param= -1, 0, 0, 0
BEGIN DESCRIPTION:
Multiple Run
END DESCRIPTION:

--- HICKORY34.f01 (steady flow) ---

Flow Title=Multiple
Number of Profiles=7
Profile Names=10-year,25-year,50-year,1pct_min,100-year,1pct_plu,500-year
River Rch & RM= HICKORY34,Reach-1,12000
     490     806    1013     712    1352    2569    1862
Boundary for River Rch & Prof#=HICKORY34,Reach-1,1
Up Type=0
Dn Type=3
Dn Slope=0.005
Boundary for River Rch & Prof#=HICKORY34,Reach-1,2
Up Type=0
Dn Type=3
Dn Slope=0.005
Boundary for River Rch & Prof#=HICKORY34,Reach-1,3
Up Type=0
Dn Type=3
Dn Slope=0.005
Boundary for River Rch & Prof#=HICKORY34,Reach-1,4
Up Type=0
Dn Type=3
Dn Slope=0.005
Boundary for River Rch & Prof#=HICKORY34,Reach-1,5
Up Type=0
Dn Type=3
Dn Slope=0.005
Boundary for River Rch & Prof#=HICKORY34,Reach-1,6
Up Type=0
Dn Type=3
Dn Slope=0.005
Boundary for River Rch & Prof#=HICKORY34,Reach-1,7
Up Type=0
Dn Type=3
Dn Slope=0.005

--- HICKORY34.g01 (geometry) ---

Geom Title=Existing Conditions

River Reach=HICKORY34,Reach-1
Reach XY= 30
      2758920.75     10178926.00      2758869.25     10179178.00
      2758455.25     10179611.00      2758302.50     10179947.00
      2758294.25     10180857.00      2758611.50     10181490.00
      2758427.00     10181970.00      2758442.50     10182148.00
      2758583.00     10182355.00      2758636.00     10182808.00
      2758914.25     10183145.00      2759191.00     10183787.00
      2759695.25     10184064.00      2759911.00     10184352.00
      2759892.25     10184752.00      2760204.75     10184923.00
      2760521.50     10185246.00      2760884.00     10185314.00
      2760992.25     10185454.00      2761170.25     10185989.00
      2761126.50     10186336.00      2761008.00     10186508.00
      2761120.25     10187058.00      2761017.25     10187148.00
      2760806.25     10187040.00      2760748.50     10187105.00
      2761039.00     10187533.00      2761020.50     10188236.00
      2761183.00     10188401.00      2761391.75     10188445.00

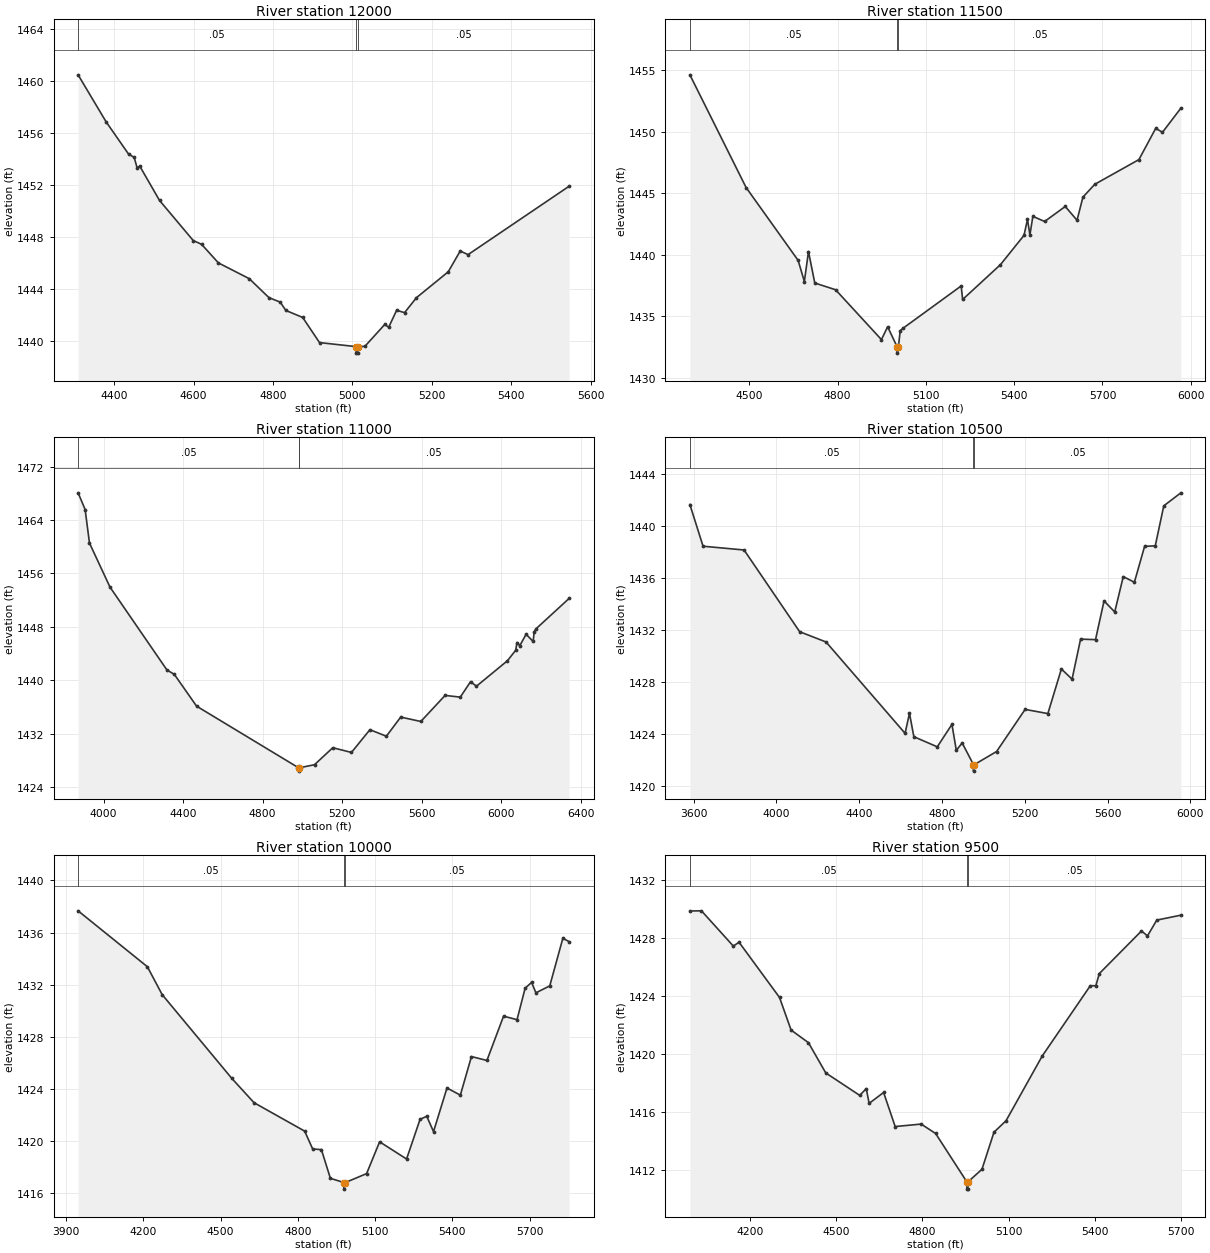
Type RM Length L Ch R = 1,12000,500,500,500
BEGIN DESCRIPTION:
HICKORY34 24.0
END DESCRIPTION:
XS GIS Cut Line= 3
      2758405.70     10178653.12      2758884.15     10179151.82
      2759430.10     10179144.00
#Sta/Elev= 30
  4308.9 1460.48  4379.5 1456.87  4436.1 1454.39  4450.2 1454.14  4457.5 1453.35
  4464.4 1453.46  4514.1 1450.83  4599.0 1447.75  4620.1 1447.46  4662.5 1446.03
  4740.2 1444.82  4789.9 1443.36  4818.2 1443.02  4832.3 1442.38  4874.8 1441.84
  4917.2 1439.91  5009.5 1439.60  5009.8 1439.10  5013.3 1439.10  5013.5 1439.60
  5031.5 1439.62  5081.5 1441.30  5091.5 1441.09  5111.5 1442.39  5131.5 1442.21
  5161.5 1443.36  5241.6 1445.35  5271.6 1446.94  5291.6 1446.67  5546.0 1451.92
#Mann=3,-1,0
  4308.9    0.05       0  5009.5    0.05       0  5013.5    0.05       0
Bank Sta=5009.5,5013.5
Exp/Cntr=0.3,0.1

Type RM Length L Ch R = 1,11500,500,500,500
BEGIN DESCRIPTION:
HICKORY34 23.0
END DESCRIPTION:
XS GIS Cut Line= 3
      2758055.72     10179003.15      2758542.59     10179508.18
      2759507.99     10179464.33
#Sta/Elev= 30
  4298.5 1454.61  4489.5 1445.45  4666.2 1439.53  4687.4 1437.81  4701.4 1440.25
  4722.8 1437.69  4793.5 1437.14  4949.2 1433.09  4970.3 1434.13  5002.8 1432.49
  5003.1 1431.99  5006.8 1432.49  5013.1 1433.82  5023.1 1434.02  5220.1 1437.45
  5225.1 1436.35  5353.5 1439.18  5433.5 1441.56  5445.4 1442.86  5453.6 1441.59
  5463.6 1443.11  5503.6 1442.69  5573.7 1443.91  5613.7 1442.79  5633.7 1444.67
  5673.8 1445.71  5823.9 1447.72  5881.0 1450.26  5904.0 1449.94  5966.4 1451.90
#Mann=3,-1,0
  4298.5    0.05       0  5002.8   0.035       0  5006.8    0.05       0
Bank Sta=5002.8,5006.8
Exp/Cntr=0.3,0.1

Type RM Length L Ch R = 1,11000,500,500,500
BEGIN DESCRIPTION:
HICKORY34 22.0
END DESCRIPTION:
XS GIS Cut Line= 3
      2757755.68     10178953.10      2758306.46     10179937.26
      2759605.67     10179603.11
#Sta/Elev= 30
  3872.2 1468.08  3907.6 1465.58  3929.5 1460.55  4032.6 1453.95  4319.1 1441.53
  4356.3 1440.87  4468.1 1436.11  4981.1 1426.87  4981.4 1426.37  4985.1 1426.87
  5061.2 1427.33  5153.1 1429.88  5247.0 1429.17  5339.9 1432.58  5422.5 1431.60
  5494.8 1434.47  5595.9 1433.81  5718.0 1437.72  5794.3 1437.46  5845.9 1439.77
  5875.8 1439.10  6031.7 1442.92  6073.1 1444.49  6079.4 1445.64  6093.7 1445.17
  6125.3 1446.88  6160.8 1445.80  6166.0 1447.25  6176.3 1447.73  6341.5 1452.25
#Mann=3,-1,0
  3872.2    0.05       0  4981.1    0.03       0  4985.1    0.05       0
Bank Sta=4981.1,4985.1
Exp/Cntr=0.3,0.1

Type RM Length L Ch R = 1,10500,500,500,500
BEGIN DESCRIPTION:
HICKORY34 21.0
END DESCRIPTION:
XS GIS Cut Line= 3
      2757255.70     10179453.13      2758280.54     10180433.72
      2759205.73     10180203.10
#Sta/Elev= 30
  3581.6 1441.66  3645.3 1438.45  3843.4 1438.16  4112.0 1431.87  4239.4 1431.08
  4621.2 1424.05  4642.5 1425.59  4663.6 1423.79  4776.8 1423.01  4847.6 1424.74
  4868.7 1422.74  4897.0 1423.31  4951.6 1421.64  4951.8 1421.14  4955.6 1421.64
  5063.3 1422.65  5201.1 1425.89  5311.0 1425.57  5376.3 1429.00  5427.9 1428.22
  5469.1 1431.30  5541.2 1431.26  5582.4 1434.24  5634.0 1433.39  5675.2 1436.11
  5729.0 1435.68  5778.3 1438.44  5829.8 1438.48  5871.0 1441.56  5953.5 1442.56
#Mann=3,-1,0
  3581.6    0.05       0  4951.6   0.035       0  4955.6    0.05       0
Bank Sta=4951.6,4955.6
Exp/Cntr=0.3,0.1

Type RM Length L Ch R = 1,10000,500,500,500
BEGIN DESCRIPTION:
HICKORY34 20.0
END DESCRIPTION:
XS GIS Cut Line= 3
      2757305.68     10180653.11      2758323.31     10180926.87
      2759138.85     10180674.83
#Sta/Elev= 30
  3946.2 1437.67  4215.4 1433.38  4272.9 1431.24  4542.3 1424.84  4629.7 1422.95
  4826.4 1420.77  4857.5 1419.40  4891.5 1419.35  4926.3 1417.15  4979.8 1416.82
  4980.0 1416.32  4983.8 1416.82  5067.0 1417.51  5117.6 1419.95  5222.3 1418.63
  5274.6 1421.67  5300.7 1421.91  5327.0 1420.73  5379.3 1424.08  5431.2 1423.53
  5474.3 1426.49  5534.4 1426.19  5599.1 1429.59  5651.4 1429.32  5682.8 1431.73
  5708.0 1432.18  5724.7 1431.38  5778.5 1431.91  5829.4 1435.56  5853.6 1435.31
#Mann=3,-1,0
  3946.2    0.05       0  4979.8    0.05       0  4983.8    0.05       0
Bank Sta=4979.8,4983.8
Exp/Cntr=0.3,0.1

Type RM Length L Ch R = 1,9500,500,500,500
BEGIN DESCRIPTION:
HICKORY34 19.0
END DESCRIPTION:
XS GIS Cut Line= 3
      2757565.54     10181456.07      2758569.31     10181357.49
      2759236.55     10181152.24
#Sta/Elev= 30
  3991.4 1429.89  4031.7 1429.90  4142.3 1427.47  4162.4 1427.73  4303.0 1423.92
  4343.2 1421.67  4403.5 1420.80  4463.8 1418.71  4581.9 1417.16  4604.5 1417.63
  4614.5 1416.61  4664.8 1417.36  4705.0 1415.01  4795.4 1415.18  4845.6 1414.53
  4954.2 1411.19  4954.4 1410.69  4957.9 1410.69  4958.2 1411.19  5006.7 1412.06
  5048.5 1414.62  5090.4 1415.41  5215.9 1419.87  5383.3 1424.73  5402.5 1424.73
  5414.7 1425.57  5561.2 1428.51  5582.1 1428.17  5614.4 1429.26  5698.1 1429.60
#Mann=3,-1,0
  3991.4    0.05       0  4954.2    0.05       0  4958.2    0.05       0
Bank Sta=4954.2,4958.2
Exp/Cntr=0.3,0.1

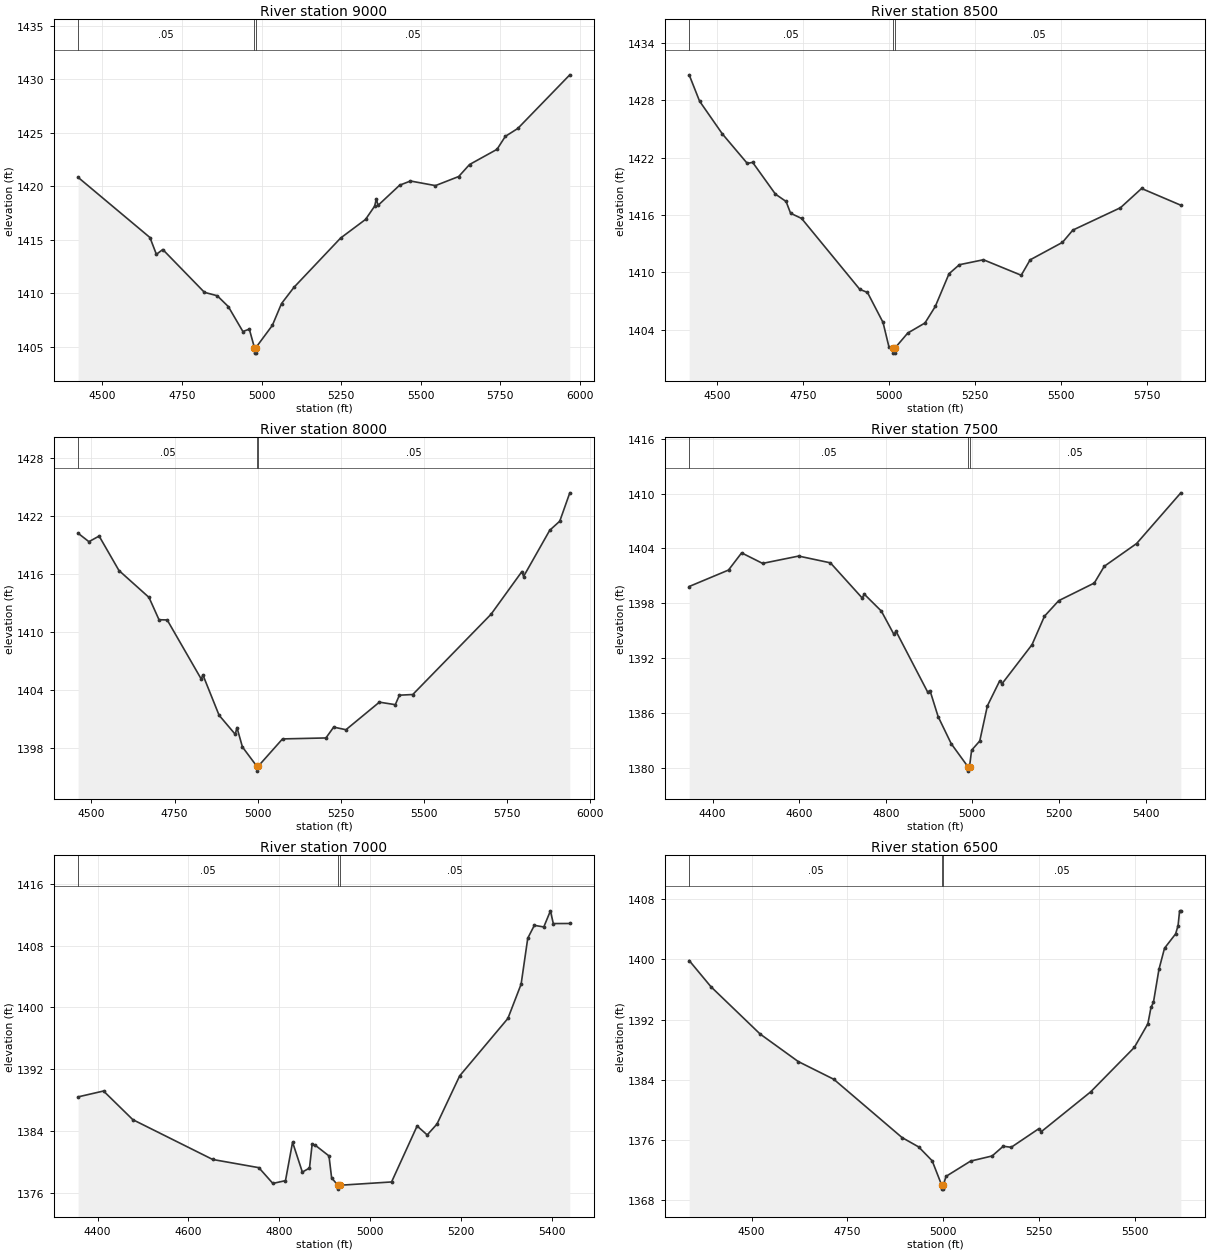
Type RM Length L Ch R = 1,9000,500,500,500
BEGIN DESCRIPTION:
HICKORY34 18.0
END DESCRIPTION:
XS GIS Cut Line= 3
      2757901.52     10181881.69      2758473.79     10181816.19
      2759405.66     10181553.12
#Sta/Elev= 30
  4424.0 1420.82  4649.6 1415.20  4669.8 1413.63  4689.9 1414.08  4820.7 1410.08
  4861.0 1409.76  4895.7 1408.75  4941.5 1406.42  4961.7 1406.64  4977.9 1404.90
  4978.2 1404.40  4981.7 1404.40  4981.9 1404.90  5034.0 1406.99  5062.8 1409.03
  5102.0 1410.55  5248.4 1415.15  5326.7 1416.89  5355.3 1418.13  5360.7 1418.82
  5365.9 1418.20  5433.9 1420.09  5467.9 1420.48  5546.3 1420.05  5619.4 1420.90
  5653.4 1422.02  5739.7 1423.44  5765.8 1424.65  5805.0 1425.39  5968.3 1430.40
#Mann=3,-1,0
  4424.0    0.05       0  4977.9    0.05       0  4981.9    0.05       0
Bank Sta=4977.9,4981.9
Exp/Cntr=0.3,0.1

Type RM Length L Ch R = 1,8500,500,500,500
BEGIN DESCRIPTION:
HICKORY34 17.0
END DESCRIPTION:
XS GIS Cut Line= 3
      2758005.69     10182553.11      2758521.41     10182283.58
      2759369.81     10182251.64
#Sta/Elev= 30
  4418.1 1430.66  4448.4 1427.91  4514.6 1424.49  4587.3 1421.40  4602.9 1421.51
  4669.2 1418.19  4700.2 1417.42  4713.3 1416.19  4745.3 1415.65  4914.6 1408.24
  4937.1 1407.91  4982.3 1404.78  4999.6 1402.21  5012.3 1402.07  5012.5 1401.57
  5016.0 1401.57  5016.3 1402.07  5054.3 1403.67  5104.4 1404.72  5134.4 1406.45
  5174.4 1409.87  5204.4 1410.81  5274.5 1411.33  5384.5 1409.71  5410.4 1411.32
  5504.6 1413.15  5534.7 1414.43  5673.4 1416.77  5734.8 1418.78  5849.0 1417.03
#Mann=3,-1,0
  4418.1    0.05       0  5012.3    0.03       0  5016.3    0.05       0
Bank Sta=5012.3,5016.3
Exp/Cntr=0.3,0.1

Type RM Length L Ch R = 1,8000,500,500,500
BEGIN DESCRIPTION:
HICKORY34 16.0
END DESCRIPTION:
XS GIS Cut Line= 3
      2758083.32     10182803.73      2758621.04     10182752.02
      2759555.72     10182653.11
#Sta/Elev= 30
  4459.8 1420.23  4492.3 1419.36  4523.0 1419.94  4582.7 1416.38  4673.1 1413.60
  4703.3 1411.29  4727.9 1411.27  4830.4 1405.16  4835.4 1405.59  4884.1 1401.42
  4932.9 1399.44  4937.9 1400.15  4954.4 1398.14  4997.8 1396.14  4998.1 1395.64
  5001.8 1396.14  5075.1 1398.97  5205.8 1399.07  5229.1 1400.19  5266.1 1399.92
  5366.7 1402.77  5414.6 1402.51  5427.0 1403.49  5467.2 1403.56  5702.9 1411.86
  5795.7 1416.27  5800.7 1415.76  5879.5 1420.54  5909.7 1421.48  5939.9 1424.41
#Mann=3,-1,0
  4459.8    0.05       0  4997.8    0.05       0  5001.8    0.05       0
Bank Sta=4997.8,5001.8
Exp/Cntr=0.3,0.1

Type RM Length L Ch R = 1,7500,500,500,500
BEGIN DESCRIPTION:
HICKORY34 15.0
END DESCRIPTION:
XS GIS Cut Line= 3
      2758265.57     10183230.82      2758914.08     10183144.73
      2759352.38     10182945.16
#Sta/Elev= 30
  4345.8 1399.84  4436.7 1401.64  4467.0 1403.52  4515.4 1402.37  4598.7 1403.17
  4672.1 1402.43  4745.4 1398.59  4750.4 1399.00  4789.8 1397.15  4818.7 1394.61
  4823.7 1394.94  4897.0 1388.27  4902.1 1388.46  4920.9 1385.61  4951.2 1382.64
  4989.5 1380.14  4989.8 1379.64  4993.5 1380.14  4998.3 1381.93  5017.1 1382.94
  5034.7 1386.78  5063.2 1389.52  5068.7 1389.21  5137.9 1393.48  5166.6 1396.59
  5199.5 1398.29  5281.7 1400.22  5304.7 1402.05  5379.4 1404.54  5481.6 1410.09
#Mann=3,-1,0
  4345.8    0.05       0  4989.5    0.05       0  4993.5    0.05       0
Bank Sta=4989.5,4993.5
Exp/Cntr=0.3,0.1

Type RM Length L Ch R = 1,7000,500,500,500
BEGIN DESCRIPTION:
HICKORY34 14.0
END DESCRIPTION:
XS GIS Cut Line= 3
      2758536.40     10183928.75      2759090.38     10183602.93
      2759355.66     10183253.14
#Sta/Elev= 30
  4357.3 1388.42  4413.2 1389.18  4477.6 1385.47  4653.4 1380.31  4754.9 1379.25
  4785.7 1377.21  4813.5 1377.57  4829.1 1382.55  4850.6 1378.68  4866.3 1379.20
  4872.1 1382.26  4878.5 1382.18  4909.2 1380.77  4915.0 1377.93  4928.7 1376.97
  4928.9 1376.47  4932.7 1376.97  5046.9 1377.40  5103.1 1384.65  5125.3 1383.49
  5146.8 1384.90  5196.7 1391.14  5302.8 1398.58  5331.9 1403.02  5346.5 1408.97
  5361.0 1410.64  5381.8 1410.43  5396.4 1412.52  5402.7 1410.87  5439.0 1410.88
#Mann=3,-1,0
  4357.3    0.05       0  4928.7    0.05       0  4932.7    0.05       0
Bank Sta=4928.7,4932.7
Exp/Cntr=0.3,0.1

Type RM Length L Ch R = 1,6500,500,500,500
BEGIN DESCRIPTION:
HICKORY34 13.0
END DESCRIPTION:
XS GIS Cut Line= 3
      2758905.72     10184353.08      2759424.00     10183940.43
      2759805.69     10183453.11
#Sta/Elev= 30
  4337.5 1399.83  4394.3 1396.35  4522.4 1390.08  4621.7 1386.43  4714.6 1384.07
  4892.4 1376.34  4935.7 1375.10  4970.9 1373.26  4995.9 1370.00  4996.1 1369.50
  4999.6 1369.50  4999.9 1370.00  5006.9 1371.19  5071.1 1373.22  5127.2 1373.90
  5156.1 1375.19  5176.9 1375.05  5249.2 1377.53  5255.5 1377.13  5383.9 1382.40
  5497.8 1388.30  5533.1 1391.44  5541.2 1393.60  5547.6 1394.28  5562.0 1398.66
  5576.5 1401.46  5605.4 1403.36  5611.8 1404.46  5615.8 1406.42  5619.0 1406.42
#Mann=3,-1,0
  4337.5    0.05       0  4995.9    0.03       0  4999.9    0.05       0
Bank Sta=4995.9,4999.9
Exp/Cntr=0.3,0.1

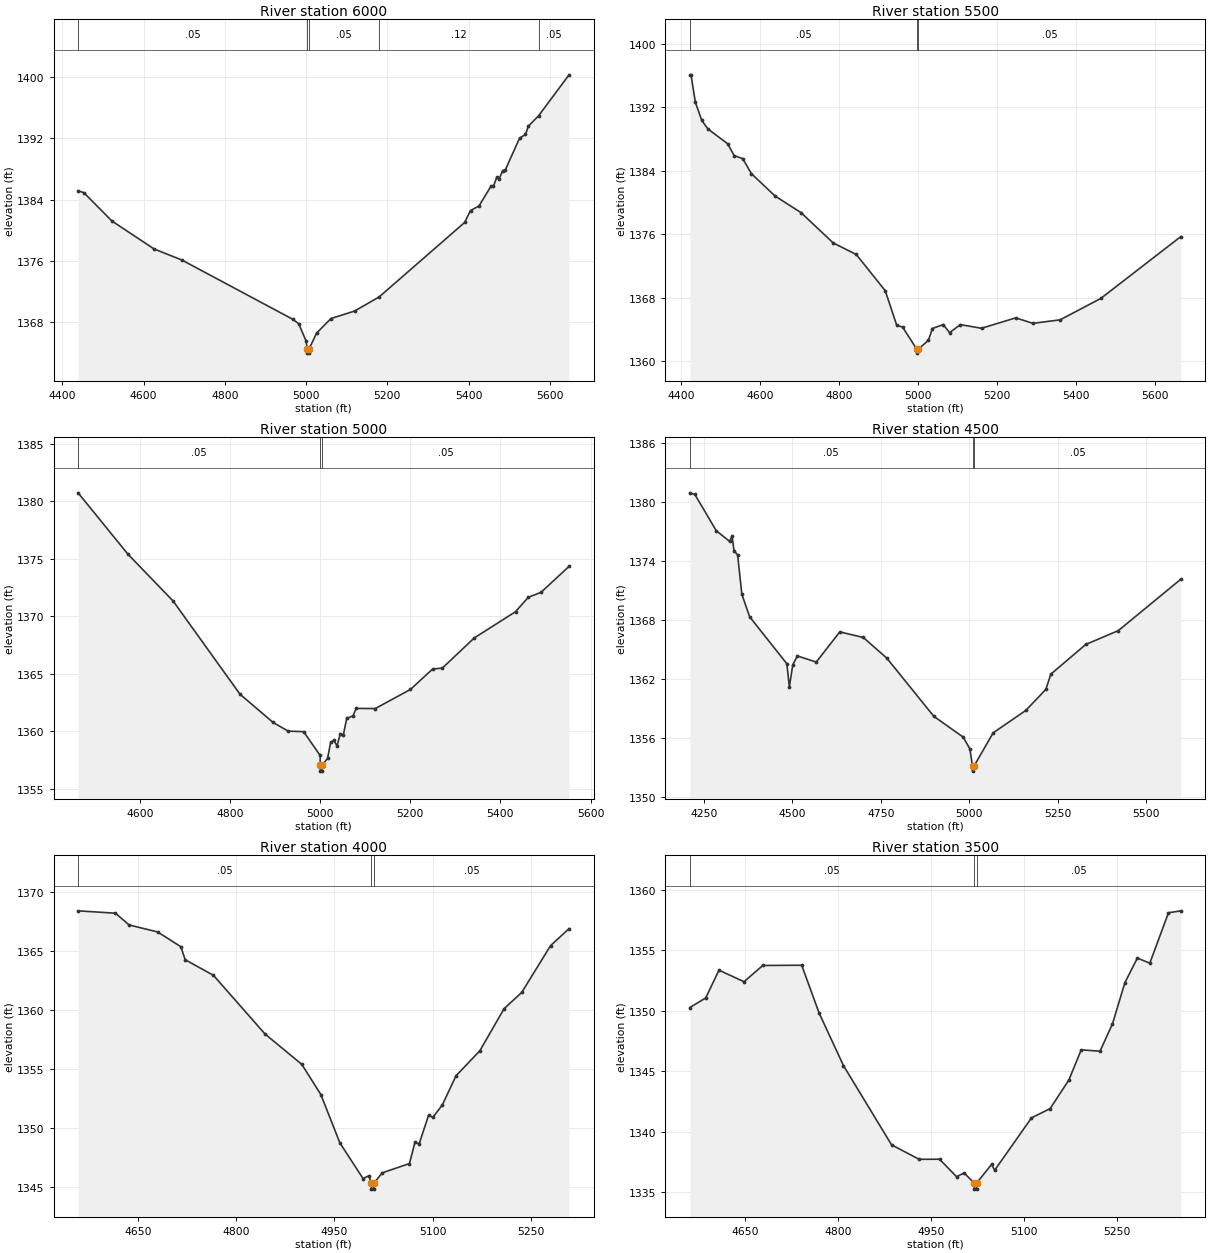
Type RM Length L Ch R = 1,6000,500,500,500
BEGIN DESCRIPTION:
HICKORY34 12.0
END DESCRIPTION:
XS GIS Cut Line= 3
      2759305.69     10184453.11      2759815.88     10184219.81
      2760205.66     10183703.15
#Sta/Elev= 30
  4439.0 1385.17  4453.3 1384.91  4522.3 1381.21  4625.9 1377.56  4694.4 1376.11
  4966.8 1368.38  4981.7 1367.80  5000.0 1365.54  5003.1 1364.44  5003.3 1363.94
  5006.8 1363.94  5007.1 1364.44  5025.9 1366.56  5061.3 1368.46  5119.5 1369.44
  5180.2 1371.30  5390.2 1381.02  5404.7 1382.58  5425.6 1383.18  5454.7 1385.73
  5461.0 1385.74  5469.3 1386.92  5475.5 1386.74  5483.8 1387.81  5490.1 1387.86
  5525.5 1392.05  5540.0 1392.52  5547.0 1393.60  5572.1 1394.96  5647.2 1400.32
#Mann=5,-1,0
  4439.0    0.05       0  5003.1    0.03       0  5007.1    0.05       0
  5180.2    0.12       0  5572.1    0.05       0
Bank Sta=5003.1,5007.1
Exp/Cntr=0.3,0.1

Type RM Length L Ch R = 1,5500,500,500,500
BEGIN DESCRIPTION:
HICKORY34 11.0
END DESCRIPTION:
XS GIS Cut Line= 3
      2759355.68     10184953.11      2759863.01     10184678.24
      2760441.67     10184351.18
#Sta/Elev= 30
  4423.0 1396.07  4425.8 1396.07  4436.8 1392.62  4453.0 1390.33  4468.5 1389.26
  4518.6 1387.39  4534.8 1385.91  4556.6 1385.52  4578.5 1383.63  4638.4 1380.81
  4704.0 1378.72  4785.8 1374.89  4843.8 1373.45  4917.0 1368.89  4946.2 1364.52
  4960.8 1364.32  4996.7 1361.53  4996.9 1361.03  5000.7 1361.53  5026.2 1362.65
  5036.4 1364.13  5063.7 1364.63  5079.7 1363.61  5107.0 1364.62  5160.5 1364.16
  5247.1 1365.47  5290.4 1364.78  5359.2 1365.22  5462.3 1367.92  5664.7 1375.71
#Mann=3,-1,0
  4423.0    0.05       0  4996.7    0.05       0  5000.7    0.05       0
Bank Sta=4996.7,5000.7
Exp/Cntr=0.3,0.1

Type RM Length L Ch R = 1,5000,500,500,500
BEGIN DESCRIPTION:
HICKORY34 10.0
END DESCRIPTION:
XS GIS Cut Line= 3
      2759755.66     10185203.12      2760239.81     10184970.35
      2760635.42     10184584.95
#Sta/Elev= 30
  4462.8 1380.73  4573.8 1375.38  4673.6 1371.33  4822.0 1363.23  4895.6 1360.77
  4928.8 1360.02  4963.3 1359.97  5000.0 1357.90  5000.2 1357.04  5000.5 1356.54
  5004.0 1356.54  5004.2 1357.04  5016.4 1357.65  5023.3 1359.05  5030.5 1359.21
  5037.5 1358.73  5044.6 1359.79  5051.6 1359.71  5058.8 1361.12  5072.9 1361.35
  5079.9 1361.99  5122.4 1361.98  5200.3 1363.64  5249.7 1365.42  5271.0 1365.49
  5341.7 1368.11  5433.6 1370.40  5461.9 1371.65  5490.1 1372.08  5552.3 1374.34
#Mann=3,-1,0
  4462.8    0.05       0  5000.2    0.03       0  5004.2    0.05       0
Bank Sta=5000.2,5004.2
Exp/Cntr=0.3,0.1

Type RM Length L Ch R = 1,4500,500,500,500
BEGIN DESCRIPTION:
HICKORY34 9.0
END DESCRIPTION:
XS GIS Cut Line= 3
      2759905.72     10185653.09      2760607.76     10185291.47
      2761040.43     10184877.80
#Sta/Elev= 30
  4210.3 1380.92  4224.2 1380.76  4285.0 1377.06  4322.7 1375.98  4329.4 1376.54
  4335.0 1375.05  4345.2 1374.60  4357.2 1370.61  4379.3 1368.31  4484.5 1363.54
  4491.5 1361.18  4501.1 1363.41  4514.0 1364.34  4567.6 1363.71  4634.1 1366.78
  4700.6 1366.21  4767.1 1364.11  4900.1 1358.19  4983.1 1356.08  5002.0 1354.88
  5009.4 1353.12  5009.6 1352.62  5013.4 1353.12  5068.0 1356.52  5160.1 1358.79
  5216.7 1360.93  5230.9 1362.48  5329.6 1365.50  5421.8 1366.91  5598.6 1372.14
#Mann=3,-1,0
  4210.3    0.05       0  5009.4    0.03       0  5013.4    0.05       0
Bank Sta=5009.4,5013.4
Exp/Cntr=0.3,0.1

Type RM Length L Ch R = 1,4000,500,500,500
BEGIN DESCRIPTION:
HICKORY34 8.0
END DESCRIPTION:
XS GIS Cut Line= 3
      2760655.67     10185753.12      2761006.35     10185484.88
      2761255.72     10185303.09
#Sta/Elev= 30
  4558.5 1368.39  4615.6 1368.19  4636.5 1367.19  4680.0 1366.60  4715.4 1365.35
  4722.2 1364.24  4765.3 1362.92  4844.2 1357.94  4900.3 1355.37  4929.4 1352.81
  4958.4 1348.72  4993.8 1345.69  5002.7 1345.92  5006.4 1345.29  5006.7 1344.79
  5010.2 1344.79  5010.4 1345.29  5023.1 1346.17  5064.8 1346.96  5073.3 1348.79
  5079.5 1348.61  5094.2 1351.09  5100.4 1350.87  5115.0 1351.93  5135.9 1354.40
  5172.4 1356.53  5209.3 1360.09  5236.3 1361.47  5280.4 1365.44  5308.6 1366.88
#Mann=3,-1,0
  4558.5    0.05       0  5006.4    0.03       0  5010.4    0.05       0
Bank Sta=5006.4,5010.4
Exp/Cntr=0.3,0.1

Type RM Length L Ch R = 1,3500,500,500,500
BEGIN DESCRIPTION:
HICKORY34 7.0
END DESCRIPTION:
XS GIS Cut Line= 3
      2760729.17     10186012.06      2761164.46     10185952.85
      2761515.57     10185918.31
#Sta/Elev= 30
  4560.7 1350.26  4586.2 1351.05  4607.6 1353.34  4648.0 1352.39  4678.3 1353.73
  4741.1 1353.75  4769.1 1349.81  4808.5 1345.46  4886.0 1338.93  4930.6 1337.73
  4963.4 1337.74  4991.1 1336.29  5003.1 1336.61  5019.3 1335.77  5019.6 1335.27
  5023.1 1335.27  5023.3 1335.77  5047.4 1337.31  5052.4 1336.83  5111.8 1341.15
  5141.9 1341.92  5172.0 1344.27  5192.1 1346.77  5222.3 1346.65  5242.4 1348.90
  5262.5 1352.31  5282.6 1354.34  5302.7 1353.92  5332.8 1358.08  5352.8 1358.24
#Mann=3,-1,0
  4560.7    0.05       0  5019.3    0.05       0  5023.3    0.05       0
Bank Sta=5019.3,5023.3
Exp/Cntr=0.3,0.1

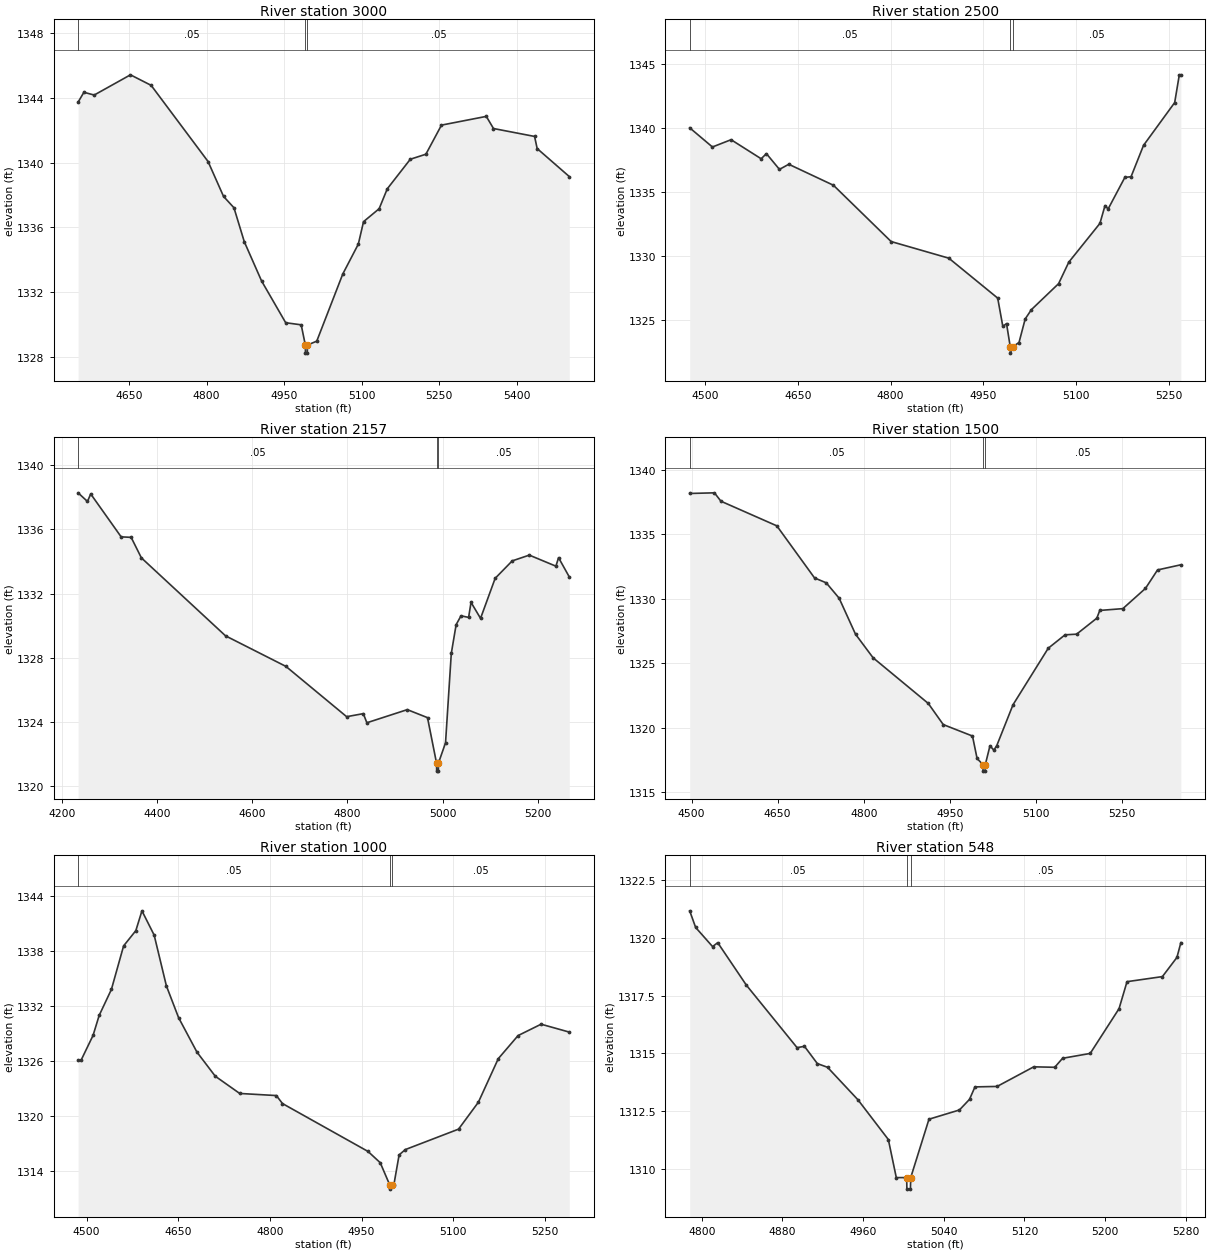
Type RM Length L Ch R = 1,3000,500,500,500
BEGIN DESCRIPTION:
HICKORY34 6.0
END DESCRIPTION:
XS GIS Cut Line= 3
      2760614.53     10186381.85      2761062.56     10186402.48
      2761561.54     10186454.67
#Sta/Elev= 30
  4551.5 1343.75  4562.7 1344.36  4582.7 1344.19  4652.8 1345.44  4692.8 1344.79
  4802.9 1340.08  4832.9 1337.92  4853.0 1337.22  4873.0 1335.12  4906.5 1332.69
  4953.1 1330.11  4983.1 1329.98  4991.1 1328.73  4991.4 1328.23  4994.9 1328.23
  4995.1 1328.73  5013.2 1328.97  5063.5 1333.12  5093.6 1334.97  5103.7 1336.36
  5133.9 1337.16  5149.6 1338.39  5194.2 1340.22  5224.3 1340.53  5254.5 1342.33
  5341.2 1342.87  5355.1 1342.12  5434.6 1341.63  5439.6 1340.88  5501.7 1339.15
#Mann=3,-1,0
  4551.5    0.05       0  4991.1    0.05       0  4995.1    0.05       0
Bank Sta=4991.1,4995.1
Exp/Cntr=0.3,0.1

Type RM Length L Ch R = 1,2500,343,343,343
BEGIN DESCRIPTION:
HICKORY34 5.0
END DESCRIPTION:
XS GIS Cut Line= 3
      2760598.95     10186548.53      2761037.98     10186836.96
      2761305.65     10186803.12
#Sta/Elev= 30
  4474.7 1340.00  4511.5 1338.50  4541.7 1339.07  4590.4 1337.58  4598.9 1337.98
  4620.0 1336.75  4635.1 1337.15  4707.4 1335.51  4800.8 1331.11  4894.2 1329.81
  4973.3 1326.69  4981.6 1324.48  4987.6 1324.70  4993.6 1322.89  4993.9 1322.39
  4997.6 1322.89  5007.8 1323.22  5017.8 1325.06  5027.9 1325.79  5071.9 1327.82
  5088.4 1329.50  5138.8 1332.53  5147.0 1333.92  5152.1 1333.66  5179.1 1336.12
  5189.2 1336.18  5209.4 1338.63  5259.8 1341.97  5267.3 1344.14  5269.8 1344.14
#Mann=3,-1,0
  4474.7    0.05       0  4993.6    0.03       0  4997.6    0.05       0
Bank Sta=4993.6,4997.6
Exp/Cntr=0.3,0.1

Type RM Length L Ch R = 1,2157,657,657,657
BEGIN DESCRIPTION:
HICKORY34 4.0
END DESCRIPTION:
XS GIS Cut Line= 3
      2760536.47     10186574.59      2761057.75     10187136.00
      2761317.68     10187194.35
#Sta/Elev= 30
  4233.9 1338.29  4253.6 1337.75  4260.4 1338.22  4324.4 1335.54  4345.4 1335.51
  4366.9 1334.23  4543.8 1329.36  4670.8 1327.45  4798.4 1324.31  4833.5 1324.50
  4840.9 1323.93  4925.9 1324.75  4968.4 1324.25  4987.4 1321.41  4987.7 1320.91
  4991.2 1320.91  4991.4 1321.41  5006.3 1322.68  5018.4 1328.26  5028.6 1330.06
  5038.9 1330.61  5054.8 1330.51  5059.9 1331.45  5079.9 1330.45  5110.6 1332.95
  5146.5 1334.04  5182.4 1334.40  5238.3 1333.71  5243.9 1334.24  5266.4 1333.04
#Mann=3,-1,0
  4233.9    0.05       0  4987.4    0.05       0  4991.4    0.05       0
Bank Sta=4987.4,4991.4
Exp/Cntr=0.3,0.1

Type RM Length L Ch R = 1,1500,500,500,500
BEGIN DESCRIPTION:
HICKORY34 3.0
END DESCRIPTION:
XS GIS Cut Line= 3
      2760432.25     10187387.06      2760926.25     10187291.30
      2761276.01     10187251.64
#Sta/Elev= 30
  4496.8 1338.18  4539.9 1338.23  4551.2 1337.58  4648.5 1335.67  4714.2 1331.63
  4734.6 1331.25  4757.0 1330.06  4785.5 1327.27  4816.1 1325.44  4912.2 1321.90
  4938.3 1320.26  4989.2 1319.37  4997.2 1317.63  5007.5 1317.15  5007.7 1316.65
  5011.2 1316.65  5011.5 1317.15  5019.6 1318.61  5026.4 1318.28  5031.5 1318.63
  5059.8 1321.80  5121.1 1326.18  5150.4 1327.22  5170.5 1327.27  5205.7 1328.51
  5210.8 1329.11  5251.0 1329.25  5290.4 1330.82  5311.4 1332.25  5352.0 1332.65
#Mann=3,-1,0
  4496.8    0.05       0  5007.5    0.05       0  5011.5    0.05       0
Bank Sta=5007.5,5011.5
Exp/Cntr=0.3,0.1

Type RM Length L Ch R = 1,1000,452,452,452
BEGIN DESCRIPTION:
HICKORY34 2.0
END DESCRIPTION:
XS GIS Cut Line= 3
      2760531.22     10187741.23      2761045.14     10187750.04
      2761321.81     10187663.44
#Sta/Elev= 30
  4486.0 1326.02  4490.7 1326.02  4510.5 1328.75  4520.5 1330.93  4540.5 1333.76
  4560.5 1338.51  4580.5 1340.17  4590.5 1342.33  4610.5 1339.68  4630.5 1334.15
  4650.5 1330.68  4680.5 1326.93  4710.5 1324.30  4750.5 1322.42  4810.5 1322.19
  4820.5 1321.32  4960.5 1316.10  4980.5 1314.87  4995.8 1312.49  4996.0 1311.99
  4999.8 1312.49  5002.9 1312.49  5011.4 1315.72  5021.5 1316.30  5108.7 1318.53
  5141.2 1321.47  5173.7 1326.21  5206.1 1328.73  5243.8 1329.97  5289.9 1329.11
#Mann=3,-1,0
  4486.0    0.05       0  4995.8    0.05       0  4999.8    0.05       0
Bank Sta=4995.8,4999.8
Exp/Cntr=0.3,0.1

Type RM Length L Ch R = 1,548,167,167,167
BEGIN DESCRIPTION:
Mapping XS 3e2721be
END DESCRIPTION:
XS GIS Cut Line= 3
      2760779.82     10188170.79      2761061.29     10188139.89
      2761191.18     10187982.66
#Sta/Elev= 30
  4788.0 1321.18  4793.9 1320.46  4810.7 1319.63  4815.8 1319.80  4844.2 1317.96
  4894.5 1315.25  4901.8 1315.31  4914.6 1314.56  4924.7 1314.40  4954.9 1312.99
  4985.0 1311.27  4992.9 1309.62  5003.2 1309.62  5003.4 1309.12  5006.9 1309.12
  5007.2 1309.62  5025.3 1312.15  5055.5 1312.55  5065.5 1313.01  5070.9 1313.55
  5092.9 1313.57  5129.2 1314.42  5150.0 1314.40  5157.8 1314.79  5185.2 1315.00
  5213.8 1316.94  5221.7 1318.11  5256.8 1318.33  5271.2 1319.16  5275.1 1319.80
#Mann=3,-1,0
  4788.0    0.05       0  5003.2    0.05       0  5007.2    0.05       0
Bank Sta=5003.2,5007.2
Exp/Cntr=0.3,0.1

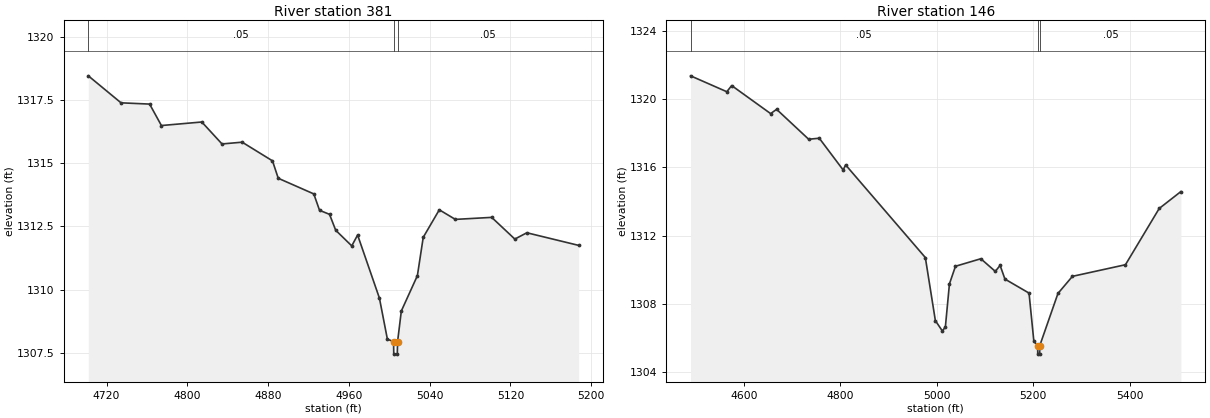
Type RM Length L Ch R = 1,381,235,235,235
BEGIN DESCRIPTION:
Mapping XS b3e8de0b
END DESCRIPTION:
XS GIS Cut Line= 4
      2760783.28     10188349.27      2760972.05     10188345.84
      2761191.73     10188222.27      2761236.34     10188218.84
#Sta/Elev= 30
  4701.9 1318.47  4734.3 1317.40  4762.6 1317.35  4774.3 1316.50  4814.3 1316.64
  4834.3 1315.77  4854.3 1315.84  4884.3 1315.10  4890.0 1314.41  4925.2 1313.79
  4930.9 1313.14  4940.8 1312.98  4946.9 1312.35  4962.8 1311.73  4968.6 1312.16
  4990.2 1309.66  4998.1 1308.03  5004.2 1307.94  5004.4 1307.44  5007.9 1307.44
  5008.2 1307.94  5011.9 1309.15  5027.8 1310.55  5033.6 1312.07  5049.5 1313.16
  5065.4 1312.78  5101.4 1312.86  5124.3 1312.00  5136.2 1312.25  5187.5 1311.75
#Mann=3,-1,0
  4701.9    0.05       0  5004.2    0.05       0  5008.2    0.05       0
Bank Sta=5004.2,5008.2
Exp/Cntr=0.3,0.1

Type RM Length L Ch R = 1,146,0,0,0
BEGIN DESCRIPTION:
HICKORY34 1.0
END DESCRIPTION:
XS GIS Cut Line= 4
      2760791.22     10188473.87      2761180.68     10188528.11
      2761291.51     10188380.35      2761730.67     10188378.11
#Sta/Elev= 30
  4489.3 1321.35  4564.5 1320.42  4574.6 1320.78  4655.4 1319.14  4667.8 1319.39
  4734.3 1317.64  4756.3 1317.70  4805.9 1315.84  4810.9 1316.14  4976.3 1310.72
  4997.1 1307.03  5011.7 1306.42  5017.9 1306.67  5026.3 1309.18  5038.8 1310.21
  5091.4 1310.65  5121.4 1309.91  5131.4 1310.26  5141.4 1309.46  5191.4 1308.64
  5201.4 1305.82  5209.2 1305.57  5209.5 1305.07  5213.4 1305.07  5213.7 1305.57
  5251.4 1308.62  5281.4 1309.62  5391.4 1310.30  5461.4 1313.59  5506.4 1314.58
#Mann=3,-1,0
  4489.3    0.05       0  5209.2    0.05       0  5213.7    0.05       0
Bank Sta=5209.2,5213.7
Exp/Cntr=0.3,0.1

Chan Stop Cuts=-1