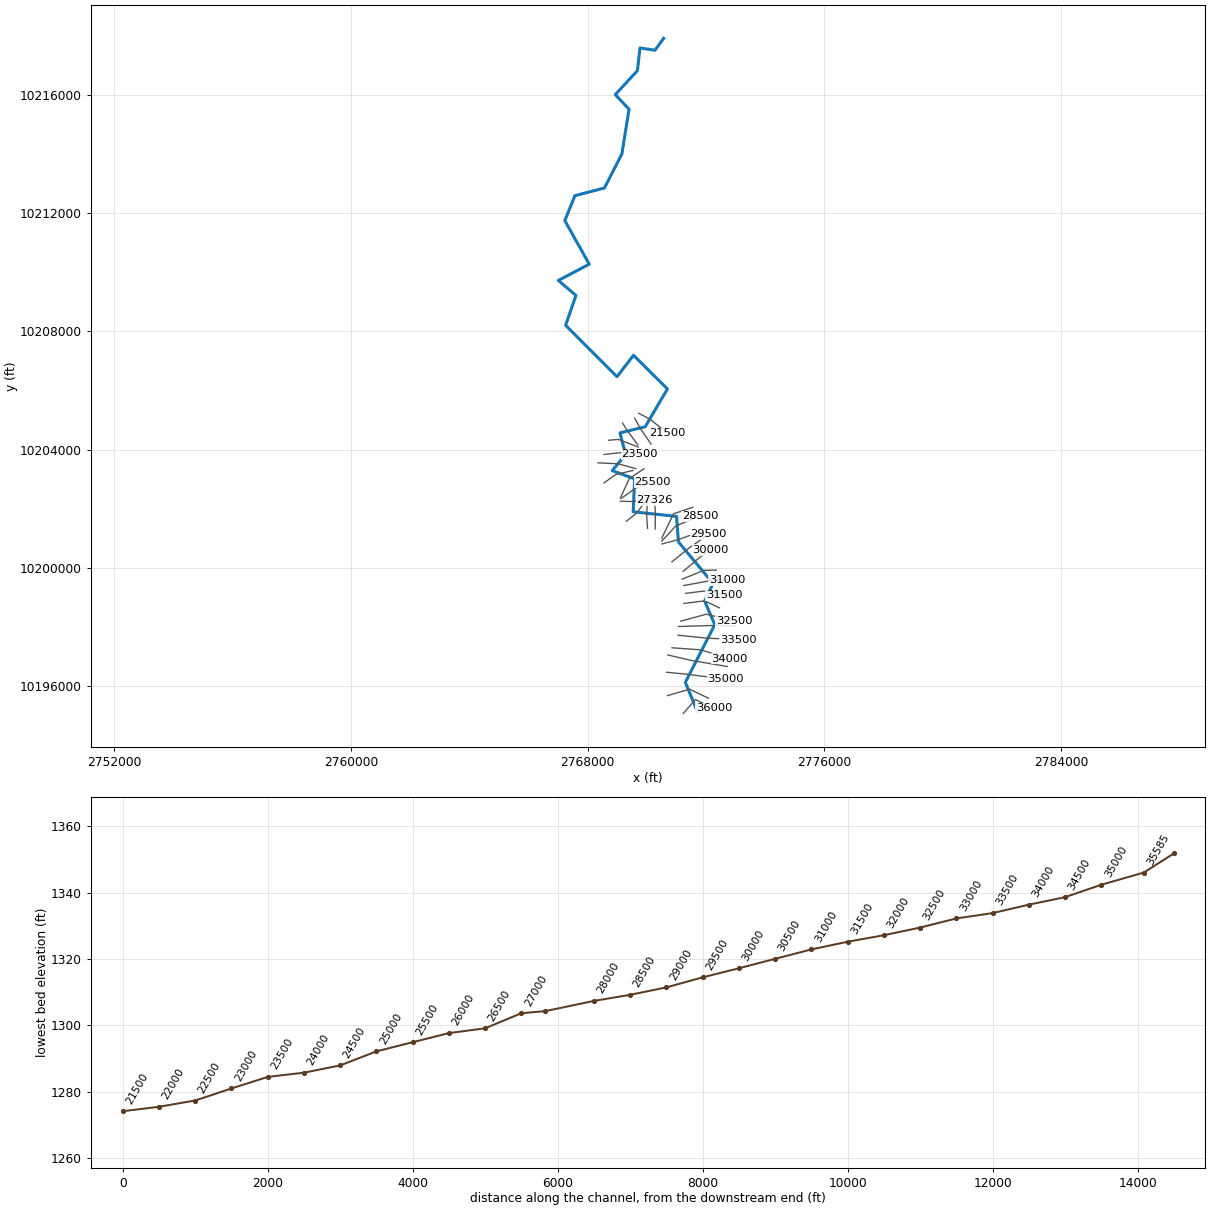
--- HICKORY37.prj (project) ---

Proj Title=HICKORY37 Base Level Engineering
Current Plan=p01
Default Exp/Contr=0.3,0.1
English Units
Geom File=g01
Flow File=f01
Plan File=p01
BEGIN DESCRIPTION:
HICKORY37
END DESCRIPTION:

--- HICKORY37.p01 (plan) ---

Plan Title=Multiple Run
Short Identifier=Multiple
Geom File=g01
Flow File=f01
Subcritical Flow
K Sum by GR= 0
Std Step Tol= 0.01
Critical Tol= 0.01
Num of Std Step Trials= 20
Max Error Tol= 0.3
Flow Tol Ratio= 0.001
Split Flow NTrial= 30
Split Flow Tol= 0.02
Split Flow Ratio= 0.02
Log Output Level= 0
Friction Slope Method= 1
Unsteady Friction Slope Method= 2
Unsteady Bridges Friction Slope Method= 1
Parabolic Critical Depth
Global Vel Dist=  1 , 1 , 1
Global Log Level= 0
CheckData=True
Encroach Param= -1, 0, 0, 0
BEGIN DESCRIPTION:
Multiple Run
END DESCRIPTION:

--- HICKORY37.f01 (steady flow) ---

Flow Title=Multiple
Number of Profiles=7
Profile Names=10-year,25-year,50-year,1pct_min,100-year,1pct_plu,500-year
River Rch & RM= HICKORY37,Reach-1,36000
     523     862     948     553    1062    2039    1406
River Rch & RM= HICKORY37,Reach-1,26000
    1007    1744    1863    1179    2497    5290    3363
River Rch & RM= HICKORY37,Reach-1,12500
    1362    2408    2724    1703    3711    8090    5019
River Rch & RM= HICKORY37,Reach-1,4500
    1593    2848    3351    2086    4609   10185    6254
Boundary for River Rch & Prof#=HICKORY37,Reach-1,1
Up Type=0
Dn Type=3
Dn Slope=0.005
Boundary for River Rch & Prof#=HICKORY37,Reach-1,2
Up Type=0
Dn Type=3
Dn Slope=0.005
Boundary for River Rch & Prof#=HICKORY37,Reach-1,3
Up Type=0
Dn Type=3
Dn Slope=0.005
Boundary for River Rch & Prof#=HICKORY37,Reach-1,4
Up Type=0
Dn Type=3
Dn Slope=0.005
Boundary for River Rch & Prof#=HICKORY37,Reach-1,5
Up Type=0
Dn Type=3
Dn Slope=0.005
Boundary for River Rch & Prof#=HICKORY37,Reach-1,6
Up Type=0
Dn Type=3
Dn Slope=0.005
Boundary for River Rch & Prof#=HICKORY37,Reach-1,7
Up Type=0
Dn Type=3
Dn Slope=0.005

--- HICKORY37.g01 (geometry) ---

Geom Title=Existing Conditions

River Reach=HICKORY37,Reach-1
Reach XY= 30
      2771712.75     10195141.00      2771304.50     10196136.00
      2772300.25     10198085.00      2771955.25     10198884.00
      2772241.25     10199477.00      2771071.50     10200881.00
      2771007.75     10201743.00      2769542.25     10201899.00
      2769591.50     10203010.00      2768835.25     10203290.00
      2769287.25     10203835.00      2769095.50     10204565.00
      2769947.75     10204773.00      2770699.75     10206050.00
      2769553.75     10207188.00      2768993.50     10206463.00
      2767258.00     10208202.00      2767608.00     10209210.00
      2767014.25     10209717.00      2768056.00     10210267.00
      2767231.00     10211740.00      2767572.50     10212581.00
      2768571.00     10212842.00      2769160.00     10213994.00
      2769401.75     10215504.00      2768937.25     10215996.00
      2769685.25     10216808.00      2769772.75     10217573.00
      2770279.50     10217499.00      2770572.25     10217899.00

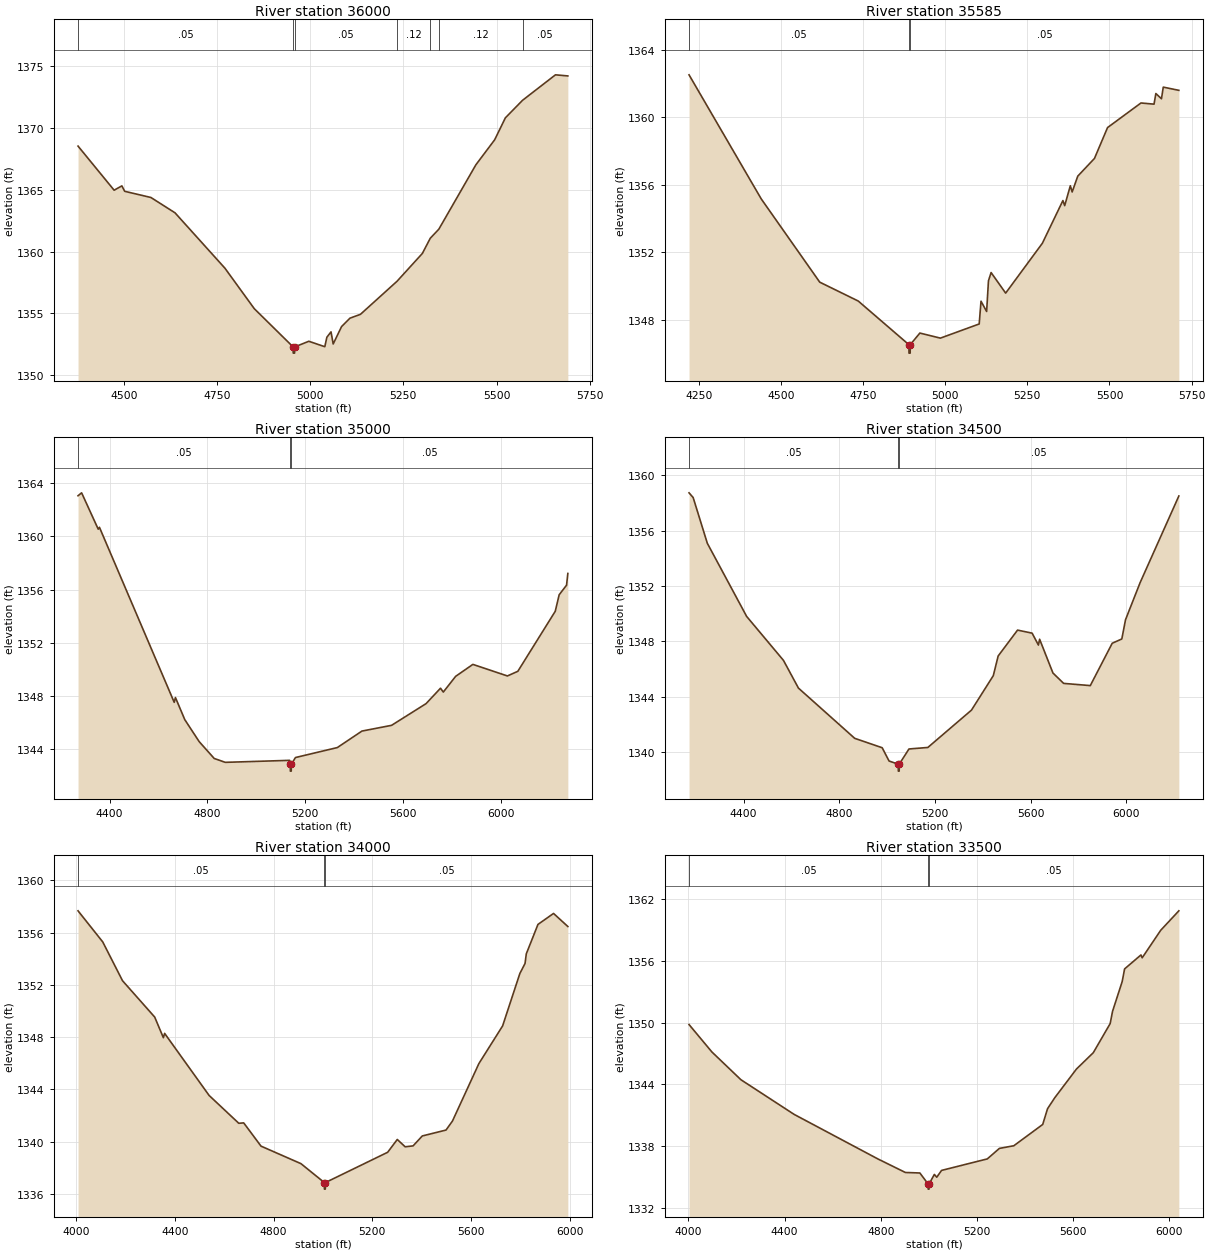
Type RM Length L Ch R = 1,36000,415,415,415
BEGIN DESCRIPTION:
HICKORY37 72.0
END DESCRIPTION:
XS GIS Cut Line= 3
      2771236.10     10195086.32      2771645.27     10195555.45
      2772266.09     10195251.35
#Sta/Elev= 30
  4377.5 1368.55  4474.3 1364.98  4495.1 1365.33  4502.7 1364.89  4573.0 1364.39
  4637.6 1363.15  4771.4 1358.67  4850.2 1355.39  4954.5 1352.29  4954.8 1351.79
  4958.3 1351.79  4958.5 1352.29  4996.5 1352.75  5039.4 1352.31  5045.0 1353.08
  5056.1 1353.51  5061.9 1352.53  5084.4 1353.94  5106.9 1354.62  5135.0 1354.93
  5232.9 1357.60  5301.1 1359.86  5322.3 1361.09  5345.2 1361.82  5444.5 1367.03
  5495.0 1369.06  5523.8 1370.84  5569.9 1372.26  5658.1 1374.32  5691.3 1374.23
#Mann=7,-1,0
  4377.5    0.05       0  4954.5    0.05       0  4958.5    0.05       0
  5232.9    0.12       0  5322.3    0.05       0  5345.2    0.12       0
  5569.9    0.05       0
Bank Sta=4954.5,4958.5
Exp/Cntr=0.3,0.1

Type RM Length L Ch R = 1,35585,585,585,585
BEGIN DESCRIPTION:
HICKORY37 71.0
END DESCRIPTION:
XS GIS Cut Line= 3
      2770701.15     10195686.35      2771449.75     10195904.00
      2772090.90     10195596.44
#Sta/Elev= 30
  4220.4 1362.53  4440.1 1355.17  4618.2 1350.23  4735.4 1349.11  4889.6 1346.52
  4889.9 1346.02  4893.4 1346.02  4893.6 1346.52  4922.9 1347.21  4985.4 1346.91
  5103.5 1347.75  5109.0 1349.10  5126.1 1348.49  5131.7 1350.31  5139.7 1350.80
  5184.0 1349.58  5295.8 1352.54  5358.2 1355.07  5363.7 1354.77  5380.8 1355.95
  5386.4 1355.58  5403.5 1356.52  5454.3 1357.57  5494.1 1359.40  5595.8 1360.86
  5635.6 1360.79  5641.1 1361.42  5658.2 1361.11  5663.7 1361.80  5711.1 1361.61
#Mann=3,-1,0
  4220.4    0.05       0  4889.6    0.03       0  4893.6    0.05       0
Bank Sta=4889.6,4893.6
Exp/Cntr=0.3,0.1

Type RM Length L Ch R = 1,35000,500,500,500
BEGIN DESCRIPTION:
HICKORY37 70.0
END DESCRIPTION:
XS GIS Cut Line= 3
      2770671.07     10196476.34      2771397.16     10196405.83
      2772660.90     10196241.37
#Sta/Elev= 30
  4270.5 1363.05  4285.2 1363.27  4353.1 1360.54  4358.1 1360.68  4664.0 1347.53
  4669.0 1347.89  4707.2 1346.23  4766.0 1344.58  4827.7 1343.31  4873.0 1343.02
  5136.0 1343.17  5139.0 1342.86  5139.3 1342.36  5142.8 1342.36  5143.0 1342.86
  5159.9 1343.38  5331.3 1344.13  5432.1 1345.37  5553.2 1345.80  5694.3 1347.43
  5753.5 1348.59  5764.9 1348.30  5815.3 1349.48  5885.9 1350.38  6027.1 1349.51
  6069.8 1349.86  6222.9 1354.37  6238.9 1355.61  6269.1 1356.33  6274.4 1357.21
#Mann=3,-1,0
  4270.5    0.05       0  5139.0    0.05       0  5143.0    0.05       0
Bank Sta=5139,5143
Exp/Cntr=0.3,0.1

Type RM Length L Ch R = 1,34500,500,500,500
BEGIN DESCRIPTION:
HICKORY37 69.0
END DESCRIPTION:
XS GIS Cut Line= 3
      2770711.10     10197061.34      2771517.43     10196872.73
      2772720.90     10196671.37
#Sta/Elev= 30
  4171.9 1358.73  4189.1 1358.39  4248.5 1355.08  4412.8 1349.80  4566.9 1346.62
  4629.4 1344.62  4864.7 1340.99  4979.6 1340.31  5008.4 1339.35  5046.9 1339.12
  5047.2 1338.62  5050.7 1338.62  5050.9 1339.12  5091.6 1340.22  5170.6 1340.33
  5353.1 1343.03  5444.3 1345.52  5464.6 1346.94  5545.7 1348.81  5606.6 1348.59
  5632.9 1347.73  5638.0 1348.15  5693.7 1345.71  5738.4 1344.96  5849.9 1344.80
  5941.6 1347.86  5981.7 1348.17  5997.2 1349.56  6058.0 1352.23  6220.2 1358.50
#Mann=3,-1,0
  4171.9    0.05       0  5046.9    0.05       0  5050.9    0.05       0
Bank Sta=5046.9,5050.9
Exp/Cntr=0.3,0.1

Type RM Length L Ch R = 1,34000,500,500,500
BEGIN DESCRIPTION:
HICKORY37 68.0
END DESCRIPTION:
XS GIS Cut Line= 3
      2770855.71     10197303.11      2771845.81     10197231.43
      2772790.91     10196926.41
#Sta/Elev= 30
  4007.3 1357.66  4107.5 1355.28  4187.7 1352.31  4318.1 1349.53  4353.3 1347.95
  4358.4 1348.28  4538.7 1343.53  4659.0 1341.40  4679.0 1341.43  4749.2 1339.65
  4911.1 1338.31  5006.0 1336.86  5006.2 1336.36  5009.7 1336.36  5010.0 1336.86
  5262.6 1339.18  5301.6 1340.16  5333.6 1339.60  5365.7 1339.67  5403.0 1340.43
  5499.1 1340.88  5525.3 1341.57  5632.5 1345.97  5728.6 1348.85  5798.5 1352.86
  5819.5 1353.63  5824.7 1354.37  5872.0 1356.62  5935.1 1357.46  5993.1 1356.46
#Mann=3,-1,0
  4007.3    0.05       0  5006.0   0.035       0  5010.0    0.05       0
Bank Sta=5006,5010
Exp/Cntr=0.3,0.1

Type RM Length L Ch R = 1,33500,500,500,500
BEGIN DESCRIPTION:
HICKORY37 67.0
END DESCRIPTION:
XS GIS Cut Line= 3
      2771061.10     10197726.34      2772053.02     10197626.87
      2773090.92     10197581.35
#Sta/Elev= 30
  4003.1 1349.83  4098.2 1347.16  4218.8 1344.46  4439.9 1341.09  4786.9 1336.77
  4902.2 1335.44  4962.5 1335.39  4996.8 1334.32  4997.1 1333.82  5000.6 1333.82
  5000.8 1334.32  5022.7 1335.25  5032.7 1334.98  5052.7 1335.64  5242.9 1336.76
  5292.9 1337.78  5353.0 1338.04  5473.1 1340.11  5493.1 1341.64  5523.2 1342.71
  5613.3 1345.50  5683.3 1347.09  5753.4 1349.92  5763.4 1351.12  5803.4 1354.01
  5813.4 1355.24  5881.5 1356.60  5886.5 1356.32  5963.6 1359.00  6038.9 1360.89
#Mann=3,-1,0
  4003.1    0.05       0  4996.8   0.035       0  5000.8    0.05       0
Bank Sta=4996.8,5000.8
Exp/Cntr=0.3,0.1

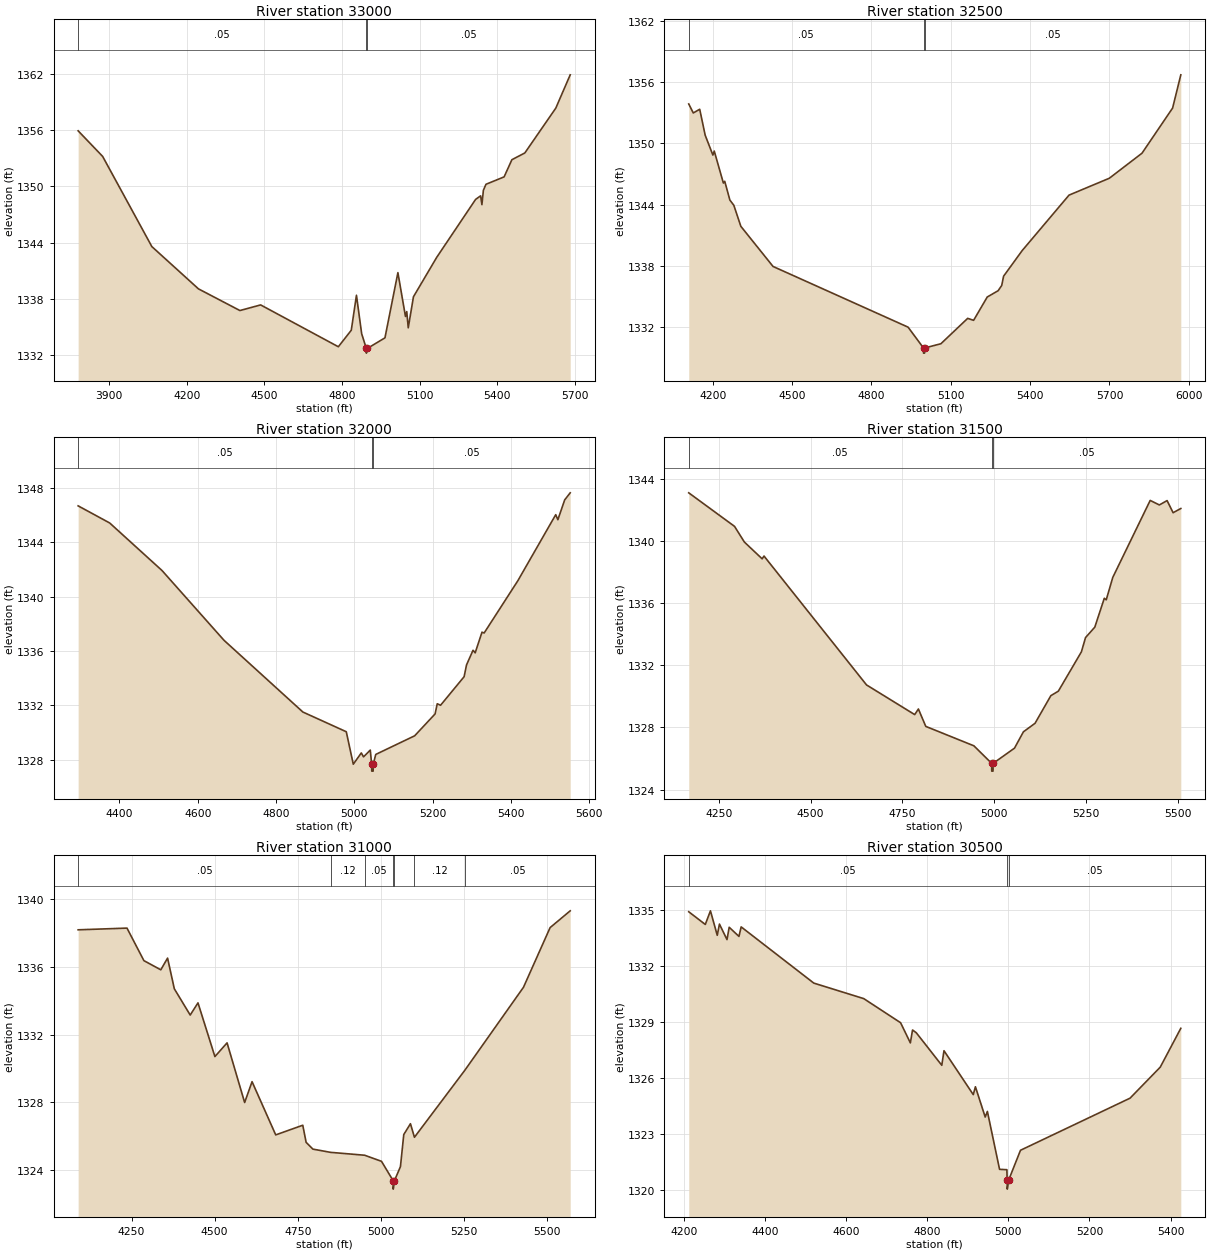
Type RM Length L Ch R = 1,33000,500,500,500
BEGIN DESCRIPTION:
HICKORY37 66.0
END DESCRIPTION:
XS GIS Cut Line= 3
      2771071.08     10198021.34      2772289.97     10198059.80
      2772970.87     10198036.35
#Sta/Elev= 30
  3780.5 1355.91  3875.2 1353.18  4065.2 1343.57  4245.3 1339.06  4405.4 1336.75
  4485.5 1337.35  4785.6 1332.89  4835.6 1334.65  4855.6 1338.38  4875.7 1334.28
  4893.7 1332.71  4893.9 1332.21  4897.7 1332.71  4965.7 1333.84  5015.7 1340.79
  5044.9 1336.12  5049.9 1336.64  5055.7 1334.91  5075.8 1338.22  5165.8 1342.43
  5315.9 1348.60  5335.2 1348.98  5340.2 1348.04  5345.9 1349.57  5355.9 1350.21
  5426.0 1351.00  5456.0 1352.83  5506.0 1353.55  5625.6 1358.33  5681.3 1361.88
#Mann=3,-1,0
  3780.5    0.05       0  4893.7    0.03       0  4897.7    0.05       0
Bank Sta=4893.7,4897.7
Exp/Cntr=0.3,0.1

Type RM Length L Ch R = 1,32500,500,500,500
BEGIN DESCRIPTION:
HICKORY37 65.0
END DESCRIPTION:
XS GIS Cut Line= 3
      2771155.70     10198203.12      2772014.88     10198438.71
      2772955.73     10198203.10
#Sta/Elev= 30
  4109.1 1353.84  4126.3 1352.96  4150.6 1353.32  4171.3 1350.78  4200.4 1348.84
  4205.6 1349.23  4240.1 1346.10  4245.3 1346.27  4264.6 1344.44  4279.7 1343.92
  4306.1 1341.87  4427.9 1337.94  4938.6 1332.00  4996.9 1329.96  4997.1 1329.46
  5000.6 1329.46  5000.9 1329.96  5062.7 1330.38  5163.9 1332.86  5186.4 1332.67
  5237.9 1334.95  5279.2 1335.57  5292.6 1336.08  5299.8 1336.99  5369.9 1339.49
  5547.2 1344.92  5699.5 1346.57  5823.1 1349.02  5938.9 1353.44  5969.9 1356.69
#Mann=3,-1,0
  4109.1    0.05       0  4996.9    0.03       0  5000.9    0.05       0
Bank Sta=4996.9,5000.9
Exp/Cntr=0.3,0.1

Type RM Length L Ch R = 1,32000,500,500,500
BEGIN DESCRIPTION:
HICKORY37 64.0
END DESCRIPTION:
XS GIS Cut Line= 3
      2771255.66     10198803.11      2771956.23     10198886.38
      2772455.65     10198653.13
#Sta/Elev= 30
  4294.5 1346.68  4375.1 1345.42  4508.7 1341.92  4667.1 1336.78  4868.5 1331.50
  4979.3 1330.05  4997.2 1327.66  5017.7 1328.49  5023.3 1328.20  5040.6 1328.70
  5044.1 1327.65  5044.4 1327.15  5047.9 1327.15  5048.1 1327.65  5054.6 1328.38
  5153.9 1329.75  5206.1 1331.36  5211.6 1332.11  5220.1 1332.00  5280.2 1334.10
  5286.4 1334.97  5303.0 1336.05  5308.5 1335.86  5325.9 1337.38  5331.4 1337.32
  5417.3 1341.16  5514.2 1346.03  5519.7 1345.66  5537.1 1347.12  5551.2 1347.64
#Mann=3,-1,0
  4294.5    0.05       0  5044.1    0.05       0  5048.1    0.05       0
Bank Sta=5044.1,5048.1
Exp/Cntr=0.3,0.1

Type RM Length L Ch R = 1,31500,500,500,500
BEGIN DESCRIPTION:
HICKORY37 63.0
END DESCRIPTION:
XS GIS Cut Line= 3
      2771315.36     10199142.71      2772140.51     10199246.88
      2772620.91     10199081.41
#Sta/Elev= 30
  4168.3 1343.11  4293.0 1340.95  4319.8 1339.94  4368.2 1338.86  4373.2 1339.04
  4652.4 1330.74  4783.5 1328.83  4793.6 1329.19  4813.7 1328.07  4944.7 1326.82
  4993.1 1325.69  4993.3 1325.19  4996.8 1325.19  4997.1 1325.69  5055.3 1326.67
  5079.5 1327.72  5111.2 1328.27  5154.3 1330.05  5174.7 1330.34  5237.4 1332.87
  5248.7 1333.79  5273.9 1334.46  5299.8 1336.32  5305.1 1336.22  5322.8 1337.66
  5424.7 1342.62  5449.7 1342.33  5470.8 1342.61  5487.1 1341.83  5508.1 1342.10
#Mann=3,-1,0
  4168.3    0.05       0  4993.1    0.05       0  4997.1    0.05       0
Bank Sta=4993.1,4997.1
Exp/Cntr=0.3,0.1

Type RM Length L Ch R = 1,31000,500,500,500
BEGIN DESCRIPTION:
HICKORY37 62.0
END DESCRIPTION:
XS GIS Cut Line= 3
      2771251.11     10199406.34      2772146.68     10199572.17
      2772716.16     10199591.34
#Sta/Elev= 30
  4089.2 1338.18  4236.2 1338.28  4287.1 1336.36  4337.9 1335.82  4358.3 1336.51
  4378.6 1334.70  4426.4 1333.15  4449.8 1333.87  4500.7 1330.70  4537.3 1331.51
  4590.2 1327.99  4612.5 1329.22  4683.7 1326.08  4765.1 1326.65  4775.2 1325.64
  4795.6 1325.24  4848.8 1325.05  4951.2 1324.88  5002.0 1324.52  5037.0 1323.38
  5037.3 1322.88  5041.0 1323.38  5059.0 1324.21  5069.0 1326.10  5089.1 1326.74
  5101.1 1325.94  5253.0 1329.90  5429.2 1334.79  5509.3 1338.31  5569.8 1339.30
#Mann=7,-1,0
  4089.2    0.05       0  4848.8    0.12       0  4951.2    0.05       0
  5037.0    0.03       0  5041.0    0.05       0  5101.1    0.12       0
  5253.0    0.05       0
Bank Sta=5037,5041
Exp/Cntr=0.3,0.1

Type RM Length L Ch R = 1,30500,500,500,500
BEGIN DESCRIPTION:
HICKORY37 61.0
END DESCRIPTION:
XS GIS Cut Line= 3
      2771196.16     10199621.36      2771925.58     10199918.70
      2772350.75     10199929.40
#Sta/Elev= 30
  4212.3 1334.90  4253.1 1334.22  4265.8 1334.95  4282.6 1333.64  4288.0 1334.24
  4306.6 1333.41  4312.0 1334.07  4336.1 1333.58  4341.5 1334.09  4520.6 1331.08
  4643.7 1330.25  4734.5 1328.96  4758.6 1327.88  4764.0 1328.57  4773.3 1328.42
  4836.1 1326.68  4841.5 1327.46  4913.7 1325.11  4919.0 1325.53  4943.1 1323.91
  4948.5 1324.21  4978.5 1321.11  4996.6 1321.09  4997.2 1320.55  4997.5 1320.05
  5001.2 1320.55  5030.1 1322.13  5300.2 1324.92  5374.6 1326.58  5425.3 1328.66
#Mann=3,-1,0
  4212.3    0.05       0  4997.2    0.05       0  5001.2    0.05       0
Bank Sta=4997.2,5001.2
Exp/Cntr=0.3,0.1

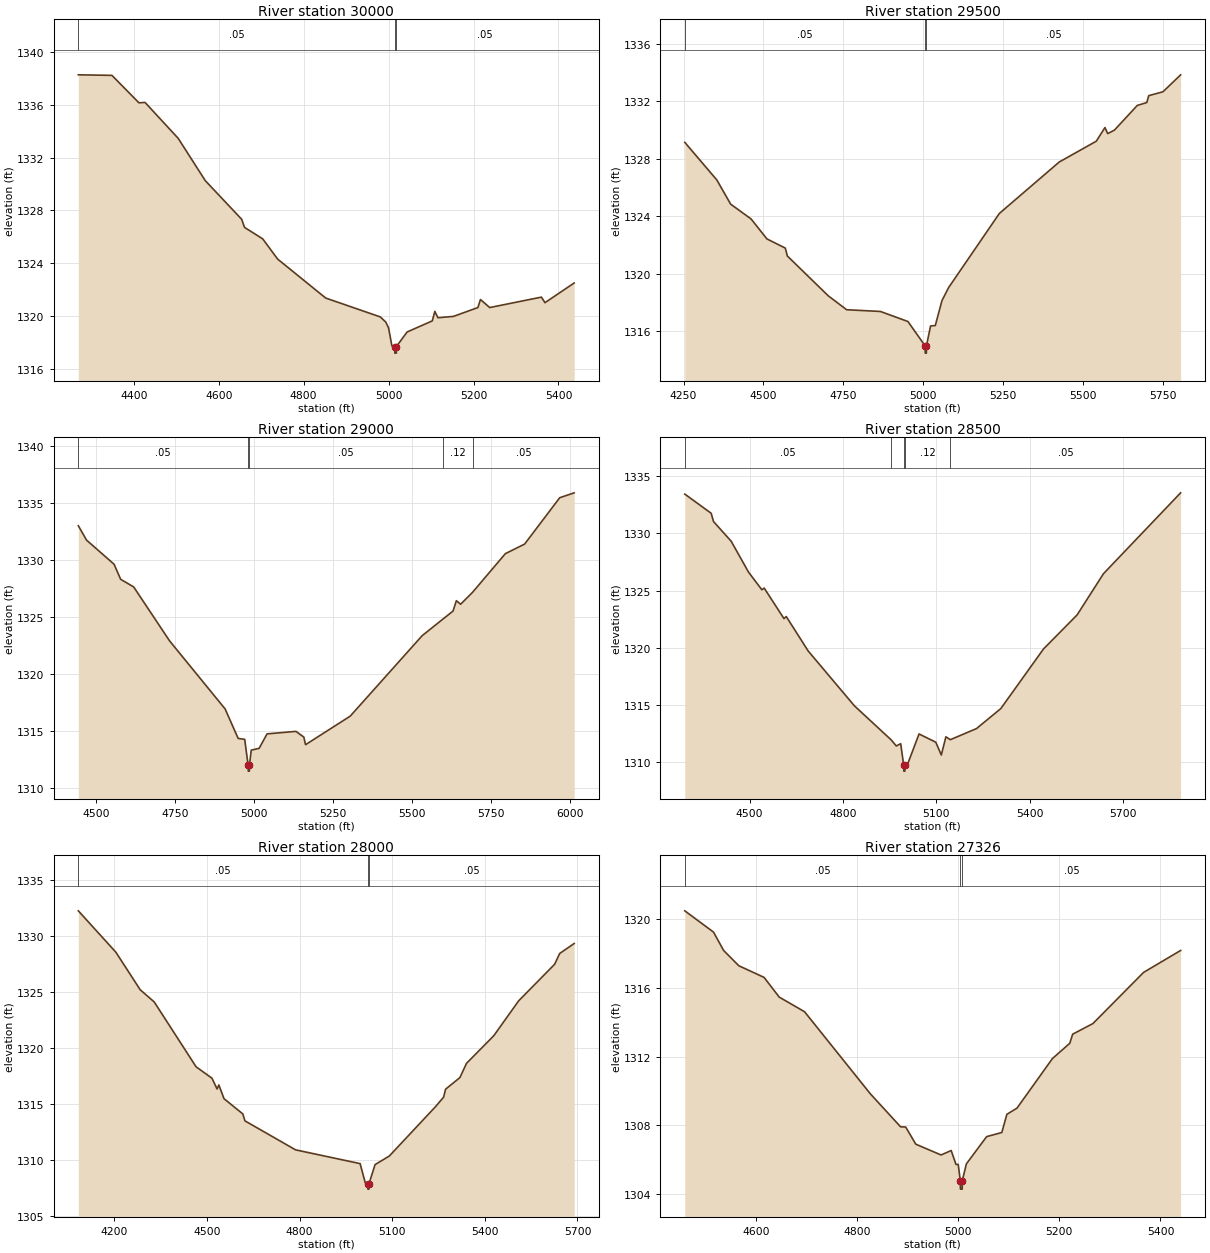
Type RM Length L Ch R = 1,30000,500,500,500
BEGIN DESCRIPTION:
HICKORY37 60.0
END DESCRIPTION:
XS GIS Cut Line= 3
      2771231.14     10199886.36      2771790.28     10200356.46
      2772148.97     10200606.09
#Sta/Elev= 30
  4269.5 1338.27  4348.6 1338.23  4412.3 1336.15  4426.6 1336.18  4504.7 1333.46
  4568.4 1330.26  4654.2 1327.33  4660.8 1326.72  4703.7 1325.85  4738.8 1324.32
  4852.0 1321.37  4980.7 1319.94  4993.7 1319.54  5000.0 1319.11  5007.8 1317.76
  5014.5 1317.70  5014.8 1317.20  5018.3 1317.20  5018.5 1317.70  5043.6 1318.80
  5102.9 1319.64  5109.0 1320.36  5116.2 1319.88  5152.8 1319.98  5210.3 1320.65
  5216.4 1321.26  5238.1 1320.65  5359.9 1321.44  5368.3 1321.02  5437.0 1322.51
#Mann=3,-1,0
  4269.5    0.05       0  5014.5    0.05       0  5018.5    0.05       0
Bank Sta=5014.5,5018.5
Exp/Cntr=0.3,0.1

Type RM Length L Ch R = 1,29500,500,500,500
BEGIN DESCRIPTION:
HICKORY37 59.0
END DESCRIPTION:
XS GIS Cut Line= 3
      2770851.12     10200206.34      2771430.60     10200676.31
      2772090.93     10201136.21
#Sta/Elev= 30
  4253.9 1329.14  4354.2 1326.52  4397.3 1324.84  4461.2 1323.81  4510.8 1322.42
  4568.3 1321.78  4574.7 1321.23  4702.6 1318.46  4760.1 1317.49  4865.7 1317.37
  4951.9 1316.67  5005.7 1314.97  5006.0 1314.47  5009.5 1314.47  5009.7 1314.97
  5022.6 1316.36  5037.4 1316.39  5058.3 1318.13  5079.3 1319.04  5237.7 1324.19
  5424.9 1327.77  5540.9 1329.22  5568.0 1330.17  5576.7 1329.75  5597.6 1329.99
  5669.2 1331.71  5698.9 1331.91  5705.0 1332.39  5749.5 1332.66  5804.7 1333.84
#Mann=3,-1,0
  4253.9    0.05       0  5005.7    0.05       0  5009.7    0.05       0
Bank Sta=5005.7,5009.7
Exp/Cntr=0.3,0.1

Type RM Length L Ch R = 1,29000,500,500,500
BEGIN DESCRIPTION:
HICKORY37 58.0
END DESCRIPTION:
XS GIS Cut Line= 3
      2770516.12     10200811.34      2771053.43     10200952.74
      2772005.71     10201303.12
#Sta/Elev= 30
  4444.4 1332.99  4470.4 1331.73  4557.7 1329.61  4578.4 1328.29  4619.7 1327.62
  4733.5 1322.88  4909.3 1316.91  4950.6 1314.32  4971.3 1314.24  4982.3 1311.95
  4982.6 1311.45  4986.1 1311.45  4986.3 1311.95  4992.0 1313.29  5017.0 1313.45
  5042.1 1314.72  5133.5 1314.94  5158.6 1314.44  5164.0 1313.77  5305.6 1316.28
  5533.3 1323.34  5598.8 1324.79  5631.1 1325.50  5641.7 1326.41  5655.2 1326.10
  5693.0 1327.15  5796.8 1330.54  5857.8 1331.38  5969.0 1335.45  6014.7 1335.88
#Mann=5,-1,0
  4444.4    0.05       0  4982.3    0.05       0  4986.3    0.05       0
  5598.8    0.12       0  5693.0    0.05       0
Bank Sta=4982.3,4986.3
Exp/Cntr=0.3,0.1

Type RM Length L Ch R = 1,28500,500,500,500
BEGIN DESCRIPTION:
HICKORY37 57.0
END DESCRIPTION:
XS GIS Cut Line= 3
      2770505.67     10200903.10      2770984.57     10201424.56
      2771805.68     10201753.11
#Sta/Elev= 30
  4292.0 1333.44  4376.8 1331.76  4384.2 1331.04  4440.9 1329.32  4497.0 1326.60
  4539.6 1325.07  4547.0 1325.22  4610.5 1322.55  4617.9 1322.73  4688.2 1319.72
  4836.8 1314.92  4955.3 1311.93  4971.2 1311.41  4985.4 1311.61  4995.1 1309.71
  4995.4 1309.21  4998.9 1309.21  4999.1 1309.71  5008.1 1309.86  5044.3 1312.46
  5098.1 1311.74  5115.8 1310.62  5130.5 1312.21  5144.8 1311.96  5228.8 1312.93
  5306.9 1314.68  5444.2 1319.90  5551.9 1322.87  5636.7 1326.48  5884.4 1333.55
#Mann=5,-1,0
  4292.0    0.05       0  4955.3    0.12       0  4995.1    0.07       0
  4999.1    0.12       0  5144.8    0.05       0
Bank Sta=4995.1,4999.1
Exp/Cntr=0.3,0.1

Type RM Length L Ch R = 1,28000,674,674,674
BEGIN DESCRIPTION:
HICKORY37 56.0
END DESCRIPTION:
XS GIS Cut Line= 3
      2770505.66     10201003.07      2770903.87     10201829.10
      2771555.65     10202053.10
#Sta/Elev= 30
  4083.0 1332.24  4204.7 1328.54  4283.6 1325.18  4328.8 1324.10  4464.5 1318.30
  4516.0 1317.28  4532.4 1316.32  4538.2 1316.68  4555.0 1315.45  4615.9 1314.09
  4622.8 1313.47  4786.7 1310.88  4995.8 1309.65  5012.5 1307.94  5020.8 1307.87
  5021.0 1307.37  5024.5 1307.37  5024.8 1307.87  5044.2 1309.56  5090.5 1310.33
  5239.8 1314.73  5266.3 1315.59  5272.7 1316.30  5319.1 1317.34  5340.5 1318.61
  5428.9 1321.08  5509.5 1324.20  5625.8 1327.46  5642.4 1328.43  5689.2 1329.32
#Mann=3,-1,0
  4083.0    0.05       0  5020.8    0.05       0  5024.8    0.05       0
Bank Sta=5020.8,5024.8
Exp/Cntr=0.3,0.1

Type RM Length L Ch R = 1,27326,326,326,326
BEGIN DESCRIPTION:
HICKORY37 55.0
END DESCRIPTION:
XS GIS Cut Line= 3
      2770286.12     10201316.32      2770290.25     10201857.00
      2770271.11     10202296.38
#Sta/Elev= 30
  4459.3 1320.50  4516.1 1319.26  4536.1 1318.19  4566.1 1317.30  4616.1 1316.62
  4646.1 1315.47  4696.1 1314.62  4826.1 1309.84  4886.1 1307.91  4896.1 1307.90
  4916.1 1306.90  4966.1 1306.27  4986.1 1306.53  4995.6 1305.72  5000.0 1305.72
  5004.1 1304.78  5004.4 1304.28  5007.9 1304.28  5008.1 1304.78  5016.1 1305.75
  5056.2 1307.34  5086.2 1307.58  5096.2 1308.64  5116.2 1309.00  5186.3 1311.89
  5220.6 1312.78  5226.3 1313.31  5266.4 1313.93  5366.5 1316.91  5439.8 1318.19
#Mann=3,-1,0
  4459.3    0.05       0  5004.1    0.03       0  5008.1    0.05       0
Bank Sta=5004.1,5008.1
Exp/Cntr=0.3,0.1

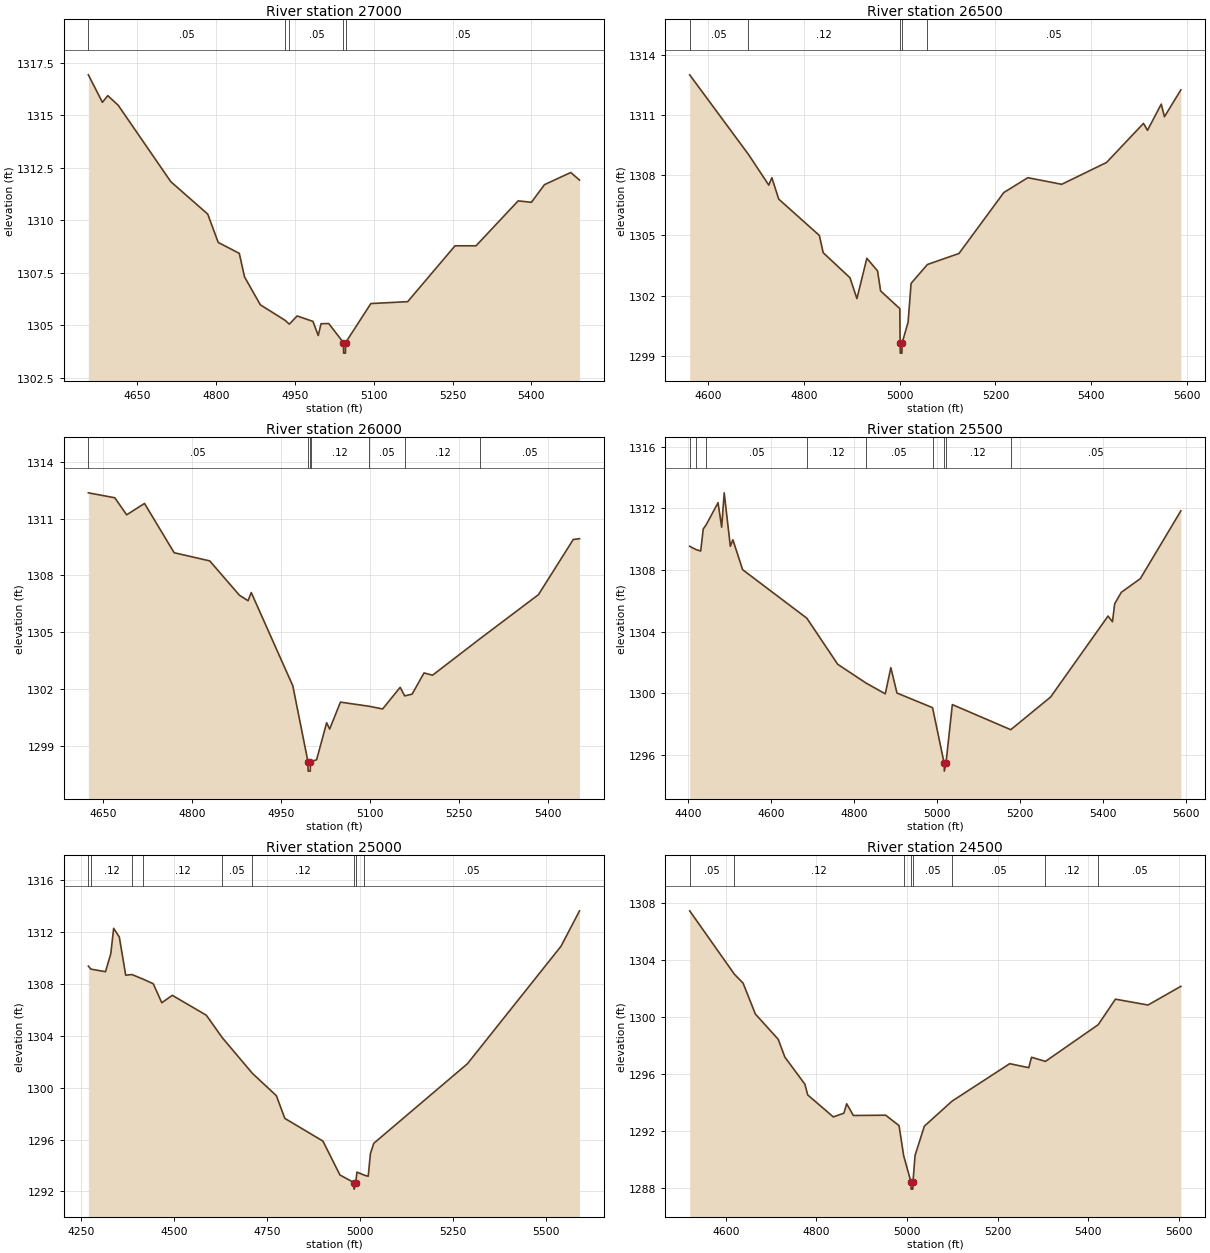
Type RM Length L Ch R = 1,27000,500,500,500
BEGIN DESCRIPTION:
HICKORY37 54.0
END DESCRIPTION:
XS GIS Cut Line= 3
      2770026.12     10201336.33      2769997.29     10201778.79
      2770026.02     10202269.75
#Sta/Elev= 30
  4556.6 1316.92  4583.4 1315.61  4593.5 1315.93  4613.5 1315.47  4713.7 1311.83
  4783.9 1310.29  4803.9 1308.94  4844.0 1308.42  4854.0 1307.30  4884.1 1305.97
  4931.4 1305.23  4939.2 1305.05  4954.2 1305.44  4984.3 1305.18  4994.3 1304.51
  4999.7 1305.07  5014.3 1305.08  5042.4 1304.17  5042.6 1303.67  5046.1 1303.67
  5046.4 1304.17  5094.5 1306.03  5164.6 1306.12  5254.8 1308.78  5294.8 1308.78
  5375.0 1310.92  5400.2 1310.85  5425.0 1311.69  5475.1 1312.27  5491.8 1311.91
#Mann=5,-1,0
  4556.6    0.05       0  4931.4    0.12       0  4939.2    0.05       0
  5042.4    0.05       0  5046.4    0.05       0
Bank Sta=5042.4,5046.4
Exp/Cntr=0.3,0.1

Type RM Length L Ch R = 1,26500,500,500,500
BEGIN DESCRIPTION:
HICKORY37 53.0
END DESCRIPTION:
XS GIS Cut Line= 3
      2769316.10     10201581.33      2769659.97     10201854.72
      2770010.88     10202326.03
#Sta/Elev= 30
  4560.7 1313.01  4683.3 1309.05  4726.1 1307.51  4732.5 1307.88  4746.9 1306.81
  4831.8 1305.00  4839.8 1304.14  4895.8 1302.89  4910.3 1301.85  4931.1 1303.86
  4953.5 1303.23  4959.9 1302.23  5000.0 1301.35  5000.7 1299.63  5001.0 1299.13
  5004.5 1299.13  5004.7 1299.63  5017.3 1300.67  5023.6 1302.61  5057.7 1303.55
  5123.7 1304.10  5217.5 1307.14  5267.6 1307.88  5338.5 1307.55  5432.3 1308.64
  5509.5 1310.59  5517.8 1310.24  5546.6 1311.55  5553.3 1310.92  5587.6 1312.26
#Mann=5,-1,0
  4560.7    0.05       0  4683.3    0.12       0  5000.7    0.07       0
  5004.7    0.12       0  5057.7    0.05       0
Bank Sta=5000.7,5004.7
Exp/Cntr=0.3,0.1

Type RM Length L Ch R = 1,26000,500,500,500
BEGIN DESCRIPTION:
HICKORY37 52.0
END DESCRIPTION:
XS GIS Cut Line= 3
      2769111.07     10202256.34      2769485.99     10202244.86
      2769936.16     10202296.34
#Sta/Elev= 30
  4624.9 1312.36  4669.5 1312.10  4689.5 1311.20  4719.6 1311.80  4769.6 1309.20
  4829.6 1308.77  4879.6 1306.96  4894.2 1306.67  4899.6 1307.10  4969.7 1302.18
  4995.2 1298.18  4995.5 1297.68  4999.1 1297.68  4999.4 1298.18  4999.7 1298.18
  5009.8 1298.28  5026.7 1300.23  5031.8 1299.90  5050.0 1301.32  5098.6 1301.10
  5121.1 1300.96  5150.7 1302.10  5158.3 1301.65  5170.8 1301.74  5190.9 1302.86
  5205.3 1302.74  5286.0 1304.68  5383.9 1306.99  5442.6 1309.90  5453.1 1309.94
#Mann=7,-1,0
  4624.9    0.05       0  4995.2    0.07       0  4999.4    0.05       0
  4999.7    0.12       0  5098.6    0.05       0  5158.3    0.12       0
  5286.0    0.05       0
Bank Sta=4995.2,4999.4
Exp/Cntr=0.3,0.1

Type RM Length L Ch R = 1,25500,500,500,500
BEGIN DESCRIPTION:
HICKORY37 51.0
END DESCRIPTION:
XS GIS Cut Line= 3
      2769151.11     10202361.33      2769637.38     10202705.25
      2770190.90     10202901.26
#Sta/Elev= 30
  4404.4 1309.54  4419.2 1309.33  4430.9 1309.23  4437.0 1310.66  4444.0 1310.93
  4472.7 1312.37  4481.4 1310.78  4487.5 1313.01  4502.3 1309.54  4508.4 1309.96
  4531.9 1308.02  4686.5 1304.87  4760.8 1301.88  4829.0 1300.66  4875.4 1299.96
  4888.8 1301.66  4903.6 1300.01  4989.3 1299.06  5017.3 1295.44  5017.6 1294.94
  5021.5 1295.44  5036.9 1299.26  5177.6 1297.63  5273.5 1299.75  5411.9 1305.01
  5422.5 1304.64  5427.9 1305.81  5443.8 1306.55  5489.7 1307.44  5587.2 1311.84
#Mann=9,-1,0
  4404.4    0.05       0  4419.2    0.12       0  4444.0    0.05       0
  4686.5    0.12       0  4829.0    0.05       0  4989.3    0.12       0
  5017.3    0.07       0  5021.5    0.12       0  5177.6    0.05       0
Bank Sta=5017.3,5021.5
Exp/Cntr=0.3,0.1

Type RM Length L Ch R = 1,25000,500,500,500
BEGIN DESCRIPTION:
HICKORY37 50.0
END DESCRIPTION:
XS GIS Cut Line= 3
      2769106.12     10202361.34      2769414.78     10203024.09
      2769905.71     10203353.13
#Sta/Elev= 30
  4268.9 1309.36  4275.7 1309.13  4315.0 1308.93  4329.3 1310.31  4337.0 1312.27
  4352.2 1311.61  4369.5 1308.66  4386.4 1308.71  4416.1 1308.36  4443.7 1308.00
  4466.6 1306.54  4494.9 1307.11  4586.4 1305.58  4629.1 1303.86  4710.1 1301.11
  4775.0 1299.38  4797.8 1297.63  4900.4 1295.88  4946.1 1293.27  4984.2 1292.68
  4984.5 1292.18  4988.5 1292.68  4991.9 1293.49  5012.2 1293.25  5022.2 1293.17
  5028.2 1294.92  5037.2 1295.71  5289.3 1301.84  5541.4 1310.90  5591.0 1313.62
#Mann=9,-1,0
  4268.9    0.05       0  4275.7    0.12       0  4386.4    0.05       0
  4416.1    0.12       0  4629.1    0.05       0  4710.1    0.12       0
  4984.2    0.07       0  4988.5    0.12       0  5012.2    0.05       0
Bank Sta=4984.2,4988.5
Exp/Cntr=0.3,0.1

Type RM Length L Ch R = 1,24500,500,500,500
BEGIN DESCRIPTION:
HICKORY37 49.0
END DESCRIPTION:
XS GIS Cut Line= 3
      2768558.63     10202876.79      2768948.71     10203155.98
      2769536.08     10203296.33
#Sta/Elev= 30
  4520.3 1307.45  4618.9 1303.01  4638.2 1302.38  4665.2 1300.22  4715.6 1298.45
  4730.3 1297.20  4774.5 1295.30  4780.7 1294.55  4837.2 1293.01  4860.5 1293.27
  4866.7 1293.93  4881.4 1293.11  4952.7 1293.13  4982.2 1292.40  4992.4 1290.29
  5008.5 1288.45  5008.8 1287.95  5012.6 1287.95  5012.9 1288.45  5017.5 1290.31
  5038.0 1292.36  5098.9 1294.11  5226.3 1296.74  5268.3 1296.46  5274.5 1297.19
  5305.2 1296.90  5421.5 1299.47  5459.6 1301.26  5531.5 1300.85  5603.9 1302.16
#Mann=8,-1,0
  4520.3    0.05       0  4618.9    0.12       0  4992.4    0.05       0
  5008.5    0.03       0  5012.9    0.05       0  5098.9    0.05       0
  5305.2    0.12       0  5421.5    0.05       0
Bank Sta=5008.5,5012.9
Exp/Cntr=0.3,0.1

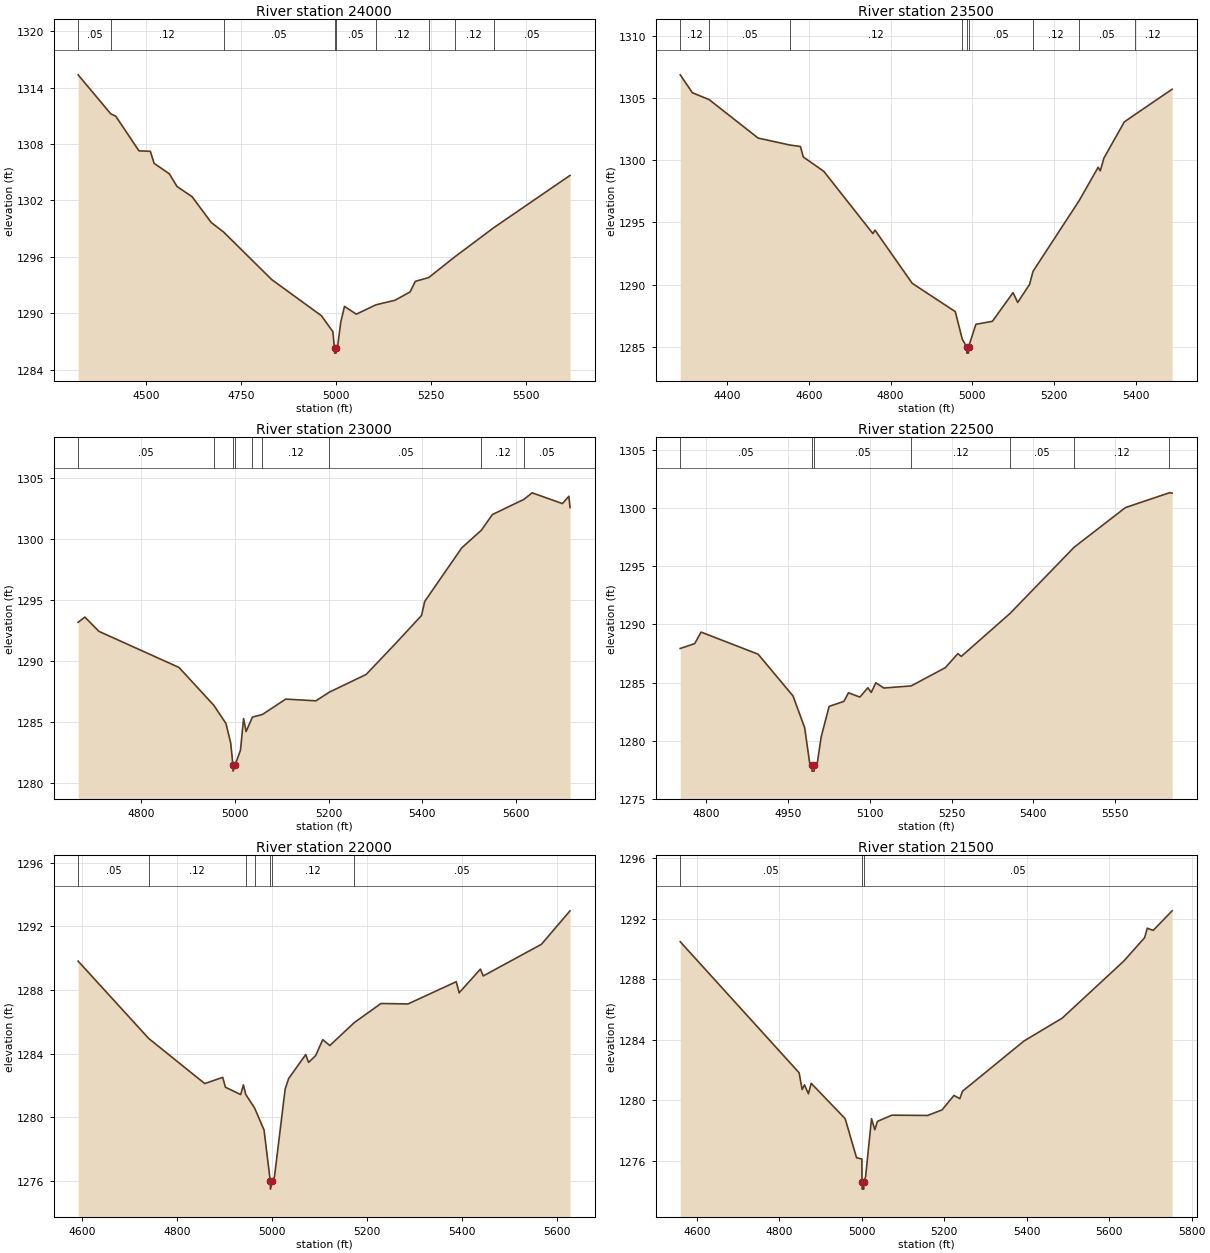
Type RM Length L Ch R = 1,24000,500,500,500
BEGIN DESCRIPTION:
HICKORY37 48.0
END DESCRIPTION:
XS GIS Cut Line= 3
      2768355.71     10203553.11      2769034.41     10203520.11
      2769628.47     10203356.80
#Sta/Elev= 30
  4320.5 1315.35  4406.5 1311.20  4419.5 1310.96  4480.7 1307.27  4510.7 1307.22
  4520.7 1305.94  4560.8 1304.83  4580.8 1303.49  4620.8 1302.39  4670.9 1299.66
  4703.7 1298.64  4830.6 1293.58  4961.2 1289.75  4991.3 1288.06  4995.9 1286.27
  4996.2 1285.77  5000.0 1285.77  5000.3 1286.27  5003.3 1286.27  5012.2 1289.05
  5022.1 1290.74  5053.2 1289.91  5104.6 1290.90  5155.1 1291.39  5194.7 1292.27
  5208.7 1293.40  5243.9 1293.80  5311.9 1295.98  5415.5 1299.11  5616.1 1304.66
#Mann=9,-1,0
  4320.5    0.05       0  4406.5    0.12       0  4703.7    0.05       0
  4995.9    0.03       0  5000.3    0.05       0  5104.6    0.12       0
  5243.9    0.05       0  5311.9    0.12       0  5415.5    0.05       0
Bank Sta=4995.9,5000.3
Exp/Cntr=0.3,0.1

Type RM Length L Ch R = 1,23500,500,500,500
BEGIN DESCRIPTION:
HICKORY37 47.0
END DESCRIPTION:
XS GIS Cut Line= 3
      2768556.14     10203836.34      2769266.90     10203914.08
      2769750.87     10203841.38
#Sta/Elev= 30
  4285.0 1306.88  4314.7 1305.44  4355.5 1304.89  4475.7 1301.79  4553.3 1301.23
  4579.3 1301.11  4586.3 1300.27  4636.6 1299.11  4756.7 1294.10  4761.8 1294.38
  4853.0 1290.10  4958.5 1287.82  4975.6 1285.60  4986.5 1284.98  4986.8 1284.48
  4990.7 1284.48  4991.0 1284.98  5008.9 1286.80  5049.3 1287.04  5099.9 1289.35
  5111.3 1288.56  5140.3 1290.01  5148.9 1291.07  5261.7 1296.75  5308.3 1299.44
  5313.4 1299.15  5322.4 1300.18  5372.3 1303.09  5397.4 1303.66  5489.4 1305.72
#Mann=9,-1,0
  4285.0    0.12       0  4355.5    0.05       0  4553.3    0.12       0
  4975.6    0.05       0  4986.5    0.03       0  4991.0    0.05       0
  5148.9    0.12       0  5261.7    0.05       0  5397.4    0.12       0
Bank Sta=4986.5,4991
Exp/Cntr=0.3,0.1

Type RM Length L Ch R = 1,23000,500,500,500
BEGIN DESCRIPTION:
HICKORY37 46.0
END DESCRIPTION:
XS GIS Cut Line= 3
      2768711.43     10204316.30      2769044.58     10204345.26
      2769710.87     10204086.43
#Sta/Elev= 30
  4665.6 1293.18  4679.9 1293.61  4710.0 1292.44  4880.7 1289.49  4954.9 1286.40
  4981.0 1284.90  4991.1 1283.30  4995.8 1281.51  4996.1 1281.01  5000.3 1281.51
  5011.9 1282.72  5018.5 1285.31  5023.9 1284.25  5037.4 1285.43  5058.5 1285.64
  5108.5 1286.90  5172.8 1286.76  5201.6 1287.47  5280.1 1288.92  5344.5 1291.52
  5398.1 1293.74  5404.9 1294.89  5483.9 1299.27  5525.9 1300.72  5549.1 1301.99
  5616.7 1303.24  5634.1 1303.77  5698.5 1302.89  5712.4 1303.49  5714.8 1302.57
#Mann=9,-1,0
  4665.6    0.05       0  4954.9    0.12       0  4995.8    0.07       0
  5000.3    0.12       0  5037.4    0.05       0  5058.5    0.12       0
  5201.6    0.05       0  5525.9    0.12       0  5616.7    0.05       0
Bank Sta=4995.8,5000.3
Exp/Cntr=0.3,0.1

Type RM Length L Ch R = 1,22500,500,500,500
BEGIN DESCRIPTION:
HICKORY37 45.0
END DESCRIPTION:
XS GIS Cut Line= 3
      2769183.93     10204895.79      2769312.31     10204684.54
      2769700.24     10204157.52
#Sta/Elev= 30
  4752.8 1287.93  4779.3 1288.35  4791.0 1289.34  4895.5 1287.44  4959.5 1283.85
  4980.9 1281.11  4990.0 1278.08  4994.1 1277.88  4994.4 1277.38  4998.3 1277.38
  4998.6 1277.88  5004.0 1278.07  5011.1 1280.32  5025.7 1282.95  5052.8 1283.38
  5061.2 1284.12  5082.0 1283.75  5096.7 1284.55  5102.9 1284.15  5111.3 1284.98
  5125.9 1284.53  5176.0 1284.71  5238.7 1286.28  5261.7 1287.49  5268.0 1287.25
  5357.2 1290.94  5474.8 1296.64  5568.8 1300.05  5649.1 1301.32  5654.4 1301.30
#Mann=7,-1,0
  4752.8    0.05       0  4994.1    0.05       0  4998.6    0.05       0
  5176.0    0.12       0  5357.2    0.05       0  5474.8    0.12       0
  5649.1    0.05       0
Bank Sta=4994.1,4998.6
Exp/Cntr=0.3,0.1

Type RM Length L Ch R = 1,22000,500,500,500
BEGIN DESCRIPTION:
HICKORY37 44.0
END DESCRIPTION:
XS GIS Cut Line= 3
      2769592.58     10205062.80      2769790.05     10204706.00
      2770144.73     10204188.84
#Sta/Elev= 30
  4592.2 1289.81  4740.8 1284.95  4858.6 1282.12  4896.4 1282.51  4902.1 1281.89
  4934.2 1281.43  4939.9 1282.04  4944.8 1281.44  4963.4 1280.59  4983.4 1279.20
  4996.5 1275.99  4996.8 1275.49  5001.0 1275.99  5005.3 1276.27  5027.8 1281.78
  5035.2 1282.44  5071.0 1283.94  5077.1 1283.45  5092.0 1283.88  5106.9 1284.88
  5121.8 1284.51  5173.2 1285.95  5229.4 1287.15  5286.2 1287.12  5387.8 1288.52
  5393.8 1287.82  5438.6 1289.31  5444.6 1288.88  5567.1 1290.87  5627.1 1292.97
#Mann=7,-1,0
  4592.2    0.05       0  4740.8    0.12       0  4944.8    0.05       0
  4963.4    0.12       0  4996.5    0.07       0  5001.0    0.12       0
  5173.2    0.05       0
Bank Sta=4996.5,5001
Exp/Cntr=0.3,0.1

Type RM Length L Ch R = 1,21500,500,500,500
BEGIN DESCRIPTION:
HICKORY37 43.0
END DESCRIPTION:
XS GIS Cut Line= 3
      2769730.95     10205227.31      2770120.32     10205021.09
      2770707.21     10204549.96
#Sta/Elev= 30
  4559.4 1290.47  4847.7 1281.83  4855.1 1280.72  4860.7 1281.03  4870.3 1280.44
  4877.1 1281.13  4959.4 1278.80  4987.1 1276.22  5000.0 1276.14  5000.3 1274.65
  5000.7 1274.15  5004.6 1274.15  5004.9 1274.65  5009.0 1274.96  5023.4 1278.80
  5031.4 1278.07  5037.8 1278.62  5073.0 1279.03  5159.4 1279.01  5194.6 1279.38
  5223.4 1280.33  5237.7 1280.12  5244.2 1280.61  5393.1 1283.92  5485.9 1285.43
  5635.2 1289.19  5685.9 1290.74  5692.3 1291.36  5706.7 1291.22  5752.6 1292.51
#Mann=3,-1,0
  4559.4    0.05       0  5000.3    0.05       0  5004.9    0.05       0
Bank Sta=5000.3,5004.9
Exp/Cntr=0.3,0.1