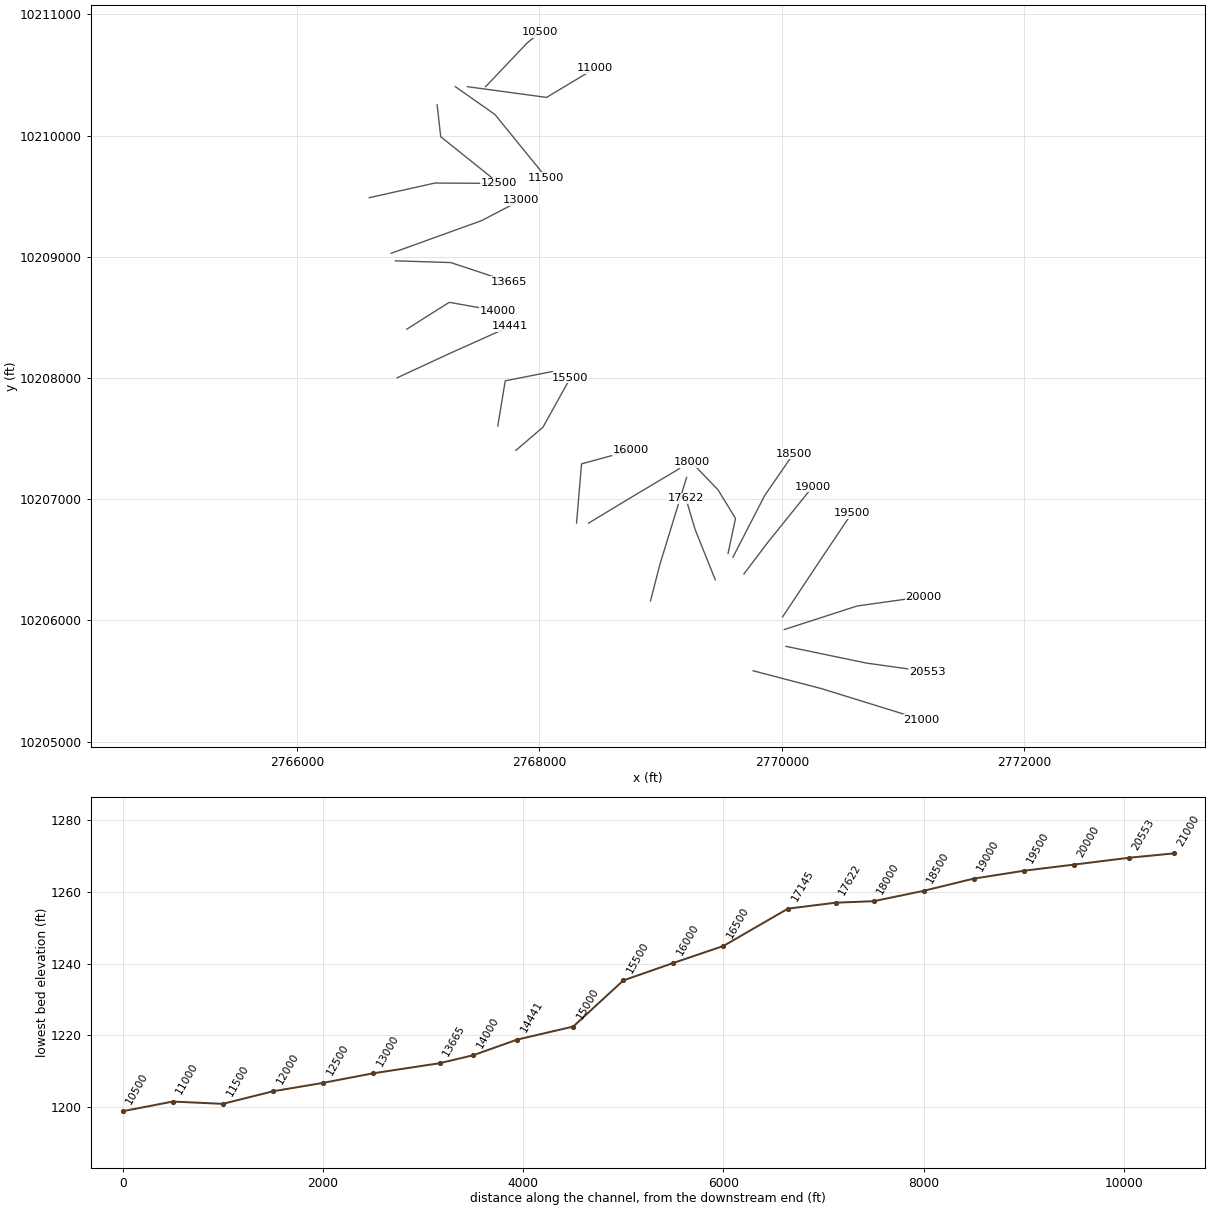
HEC-RAS study HICKORY37.prj: HICKORY37 Base Level Engineering

--- HICKORY37.g01 (geometry) --- (continued)

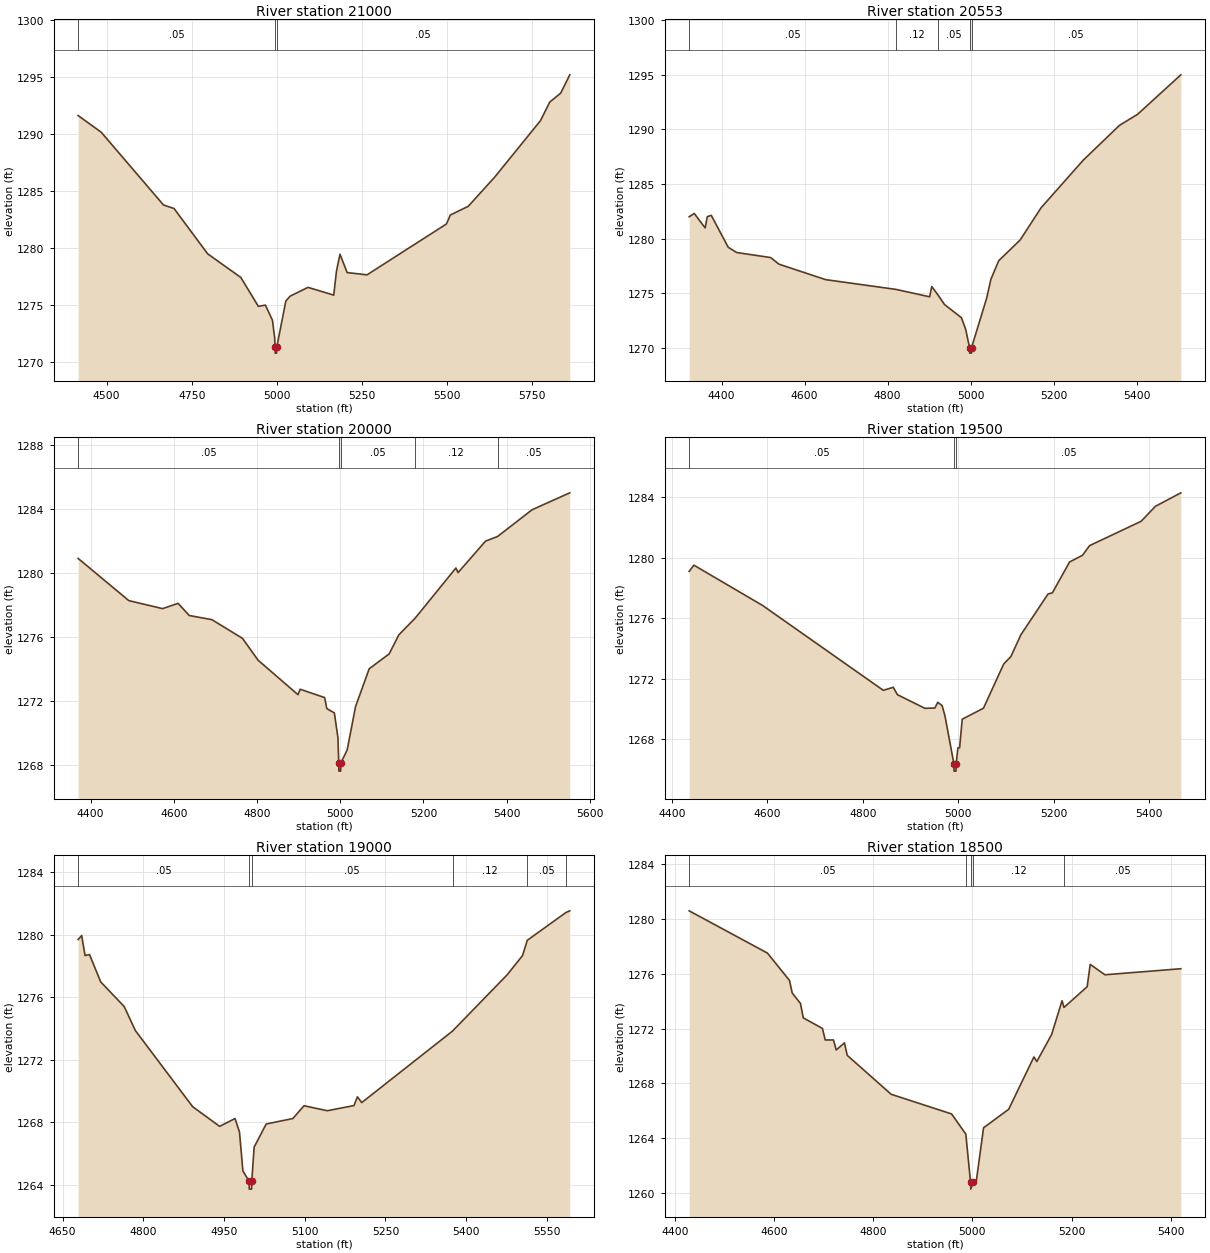
Type RM Length L Ch R = 1,21000,447,447,447
BEGIN DESCRIPTION:
HICKORY37 42.0
END DESCRIPTION:
XS GIS Cut Line= 3
      2769762.79     10205584.67      2770327.78     10205436.90
      2771151.15     10205182.06
#Sta/Elev= 30
  4416.0 1291.63  4483.8 1290.17  4667.1 1283.77  4698.1 1283.46  4796.9 1279.48
  4894.5 1277.40  4946.1 1274.86  4966.8 1274.97  4987.5 1273.64  4993.9 1272.14
  4995.3 1271.25  4995.6 1270.75  4999.6 1270.75  5000.0 1271.25  5026.9 1275.33
  5039.7 1275.76  5092.0 1276.53  5167.8 1275.85  5175.8 1277.97  5186.2 1279.44
  5207.2 1277.83  5265.6 1277.63  5499.1 1282.10  5510.7 1282.89  5563.1 1283.65
  5640.0 1286.18  5775.7 1291.18  5803.1 1292.82  5835.2 1293.60  5861.9 1295.21
#Mann=3,-1,0
  4416.0    0.05       0  4995.3    0.05       0  5000.0    0.05       0
Bank Sta=4995.3,5000
Exp/Cntr=0.3,0.1

Type RM Length L Ch R = 1,20553,553,553,553
BEGIN DESCRIPTION:
HICKORY37 41.0
END DESCRIPTION:
XS GIS Cut Line= 3
      2770033.60     10205786.06      2770697.50     10205648.00
      2771198.93     10205577.92
#Sta/Elev= 30
  4321.9 1282.01  4334.2 1282.31  4360.4 1280.99  4365.5 1282.02  4375.1 1282.14
  4416.0 1279.22  4436.4 1278.74  4518.1 1278.28  4538.5 1277.67  4650.7 1276.26
  4819.8 1275.37  4901.2 1274.69  4906.3 1275.63  4921.6 1274.84  4936.9 1273.99
  4977.7 1272.78  4987.9 1271.73  4997.4 1270.04  4997.7 1269.54  5001.8 1269.54
  5002.1 1270.04  5038.6 1274.57  5048.7 1276.29  5067.6 1277.99  5119.3 1279.89
  5169.8 1282.84  5270.8 1287.17  5358.5 1290.37  5402.1 1291.38  5506.3 1294.99
#Mann=5,-1,0
  4321.9    0.05       0  4819.8    0.12       0  4921.6    0.05       0
  4997.4    0.05       0  5002.1    0.05       0
Bank Sta=4997.4,5002.1
Exp/Cntr=0.3,0.1

Type RM Length L Ch R = 1,20000,500,500,500
BEGIN DESCRIPTION:
HICKORY37 40.0
END DESCRIPTION:
XS GIS Cut Line= 3
      2770019.69     10205924.94      2770619.04     10206118.71
      2771165.53     10206195.78
#Sta/Elev= 30
  4370.1 1280.92  4492.0 1278.28  4573.1 1277.78  4610.4 1278.11  4637.2 1277.35
  4691.7 1277.09  4765.3 1275.92  4802.5 1274.56  4898.6 1272.40  4903.8 1272.74
  4962.6 1272.22  4967.9 1271.53  4986.0 1271.26  4994.6 1269.72  4996.6 1268.12
  4997.0 1267.62  5001.1 1267.62  5001.4 1268.12  5016.8 1268.94  5037.0 1271.66
  5069.8 1274.02  5117.8 1274.95  5141.0 1276.14  5180.1 1277.18  5278.2 1280.32
  5283.3 1280.03  5349.4 1282.00  5378.3 1282.29  5461.2 1283.96  5551.9 1285.02
#Mann=5,-1,0
  4370.1    0.05       0  4996.6    0.05       0  5001.4    0.05       0
  5180.1    0.12       0  5378.3    0.05       0
Bank Sta=4996.6,5001.4
Exp/Cntr=0.3,0.1

Type RM Length L Ch R = 1,19500,500,500,500
BEGIN DESCRIPTION:
HICKORY37 39.0
END DESCRIPTION:
XS GIS Cut Line= 3
      2770005.53     10206029.43      2770317.44     10206499.22
      2770577.44     10206886.55
#Sta/Elev= 30
  4436.1 1279.10  4446.0 1279.51  4590.3 1276.84  4842.9 1271.24  4863.9 1271.44
  4872.6 1270.95  4930.1 1270.05  4951.1 1270.07  4957.1 1270.45  4966.2 1270.23
  4972.2 1269.55  4990.8 1266.40  4991.1 1265.90  4995.3 1265.90  4995.7 1266.40
  4999.3 1267.44  5002.9 1267.44  5008.3 1269.33  5052.9 1270.06  5095.3 1272.98
  5110.3 1273.47  5131.3 1274.91  5188.3 1277.61  5197.3 1277.68  5233.3 1279.72
  5260.3 1280.16  5275.3 1280.80  5383.3 1282.41  5413.3 1283.40  5466.5 1284.29
#Mann=3,-1,0
  4436.1    0.05       0  4990.8    0.05       0  4995.7    0.05       0
Bank Sta=4990.8,4995.7
Exp/Cntr=0.3,0.1

Type RM Length L Ch R = 1,19000,500,500,500
BEGIN DESCRIPTION:
HICKORY37 38.0
END DESCRIPTION:
XS GIS Cut Line= 3
      2769686.39     10206383.28      2769880.03     10206639.54
      2770251.75     10207101.32
#Sta/Elev= 30
  4678.8 1279.69  4685.4 1279.95  4691.7 1278.67  4700.0 1278.73  4720.8 1276.98
  4764.5 1275.40  4785.3 1273.86  4891.7 1268.99  4941.8 1267.73  4970.5 1268.23
  4978.8 1267.36  4985.1 1264.88  4996.7 1264.21  4997.0 1263.71  5001.2 1263.71
  5001.6 1264.21  5006.0 1266.40  5028.4 1267.88  5078.0 1268.23  5098.8 1269.05
  5142.0 1268.73  5191.6 1269.06  5198.0 1269.62  5206.0 1269.25  5374.8 1273.83
  5476.3 1277.43  5505.1 1278.67  5513.7 1279.64  5586.0 1281.43  5592.8 1281.53
#Mann=6,-1,0
  4678.8    0.05       0  4996.7    0.05       0  5001.6    0.05       0
  5374.8    0.12       0  5513.7    0.05       0  5586.0    0.12       0
Bank Sta=4996.7,5001.6
Exp/Cntr=0.3,0.1

Type RM Length L Ch R = 1,18500,500,500,500
BEGIN DESCRIPTION:
HICKORY37 37.0
END DESCRIPTION:
XS GIS Cut Line= 3
      2769596.11     10206522.17      2769857.42     10207030.09
      2770096.09     10207376.30
#Sta/Elev= 30
  4428.8 1280.58  4586.7 1277.50  4631.1 1275.51  4636.7 1274.59  4653.3 1273.83
  4658.9 1272.78  4697.6 1272.01  4703.2 1271.17  4719.8 1271.17  4725.4 1270.44
  4742.0 1270.96  4747.6 1270.05  4836.3 1267.21  4958.1 1265.78  4986.8 1264.31
  4996.4 1260.80  4996.8 1260.30  5001.4 1260.80  5007.7 1260.82  5022.6 1264.77
  5073.3 1266.12  5124.1 1269.93  5130.1 1269.60  5159.9 1271.57  5180.9 1274.03
  5184.8 1273.54  5231.6 1275.05  5237.7 1276.68  5267.4 1275.92  5420.5 1276.36
#Mann=5,-1,0
  4428.8    0.05       0  4986.8    0.12       0  4996.4    0.07       0
  5001.4    0.12       0  5184.8    0.05       0
Bank Sta=4996.4,5001.4
Exp/Cntr=0.3,0.1

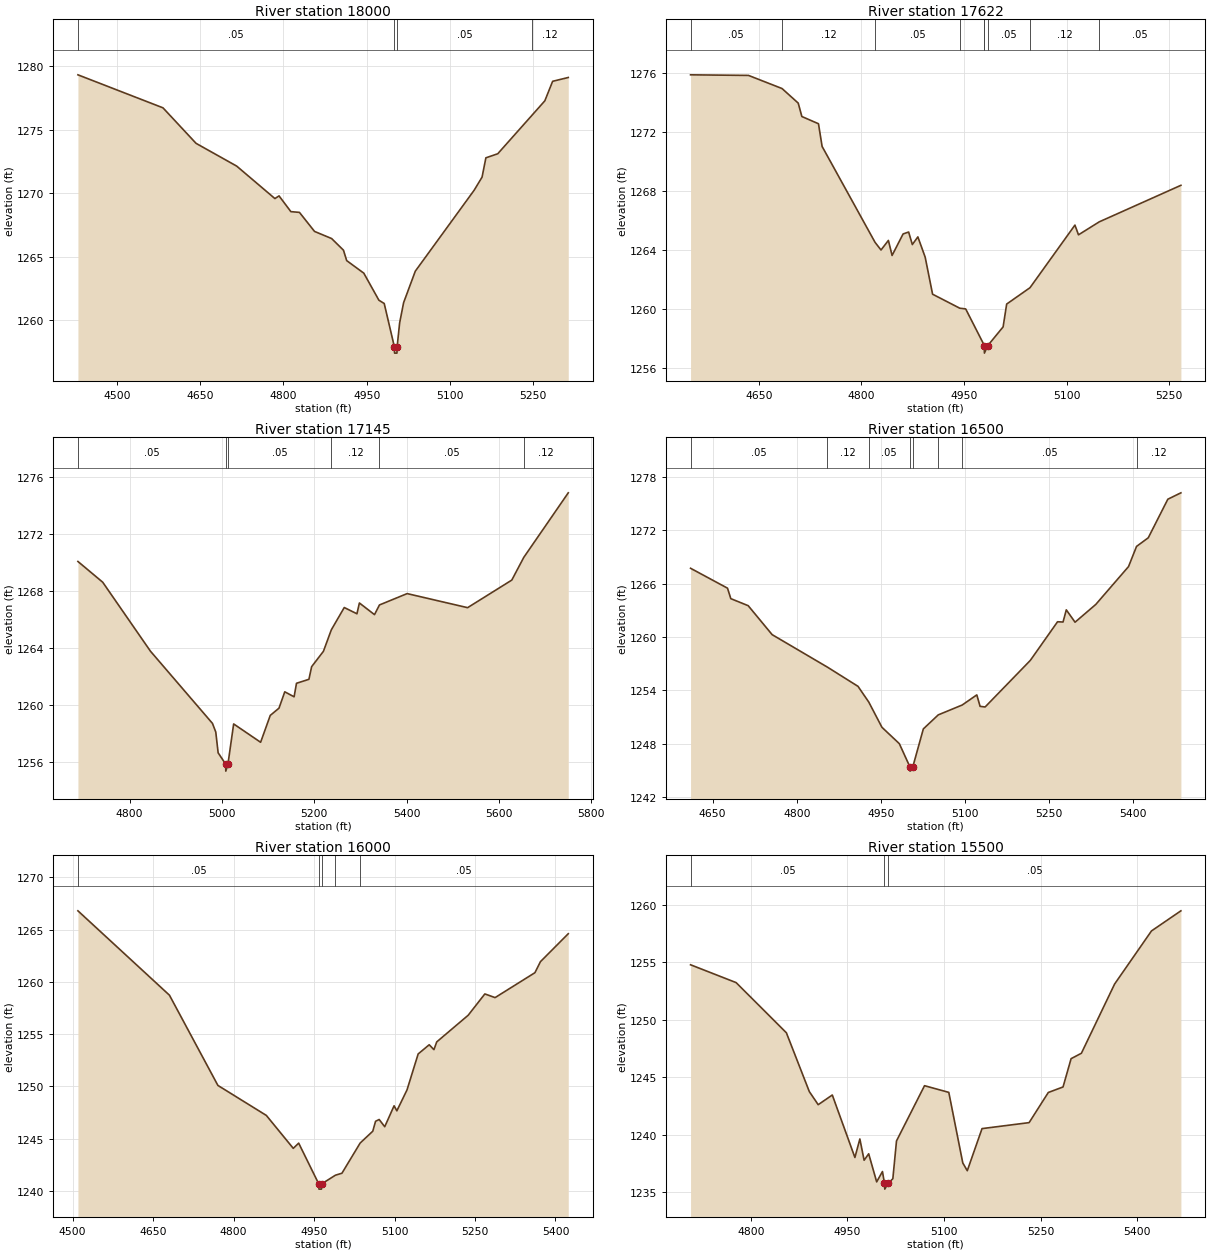
Type RM Length L Ch R = 1,18000,378,378,378
BEGIN DESCRIPTION:
HICKORY37 36.0
END DESCRIPTION:
XS GIS Cut Line= 4
      2769555.68     10206553.09      2769616.95     10206841.62
      2769473.07     10207076.96      2769255.68     10207303.12
#Sta/Elev= 30
  4429.2 1279.34  4582.6 1276.74  4642.3 1273.94  4715.5 1272.15  4784.5 1269.59
  4792.0 1269.80  4813.3 1268.56  4828.8 1268.50  4856.0 1267.00  4886.8 1266.44
  4908.2 1265.52  4914.0 1264.70  4944.9 1263.71  4972.1 1261.58  4981.7 1261.32
  5000.0 1257.91  5000.4 1257.41  5004.7 1257.41  5005.0 1257.91  5009.5 1259.79
  5016.7 1261.39  5037.8 1263.87  5144.0 1270.25  5158.2 1271.28  5165.1 1272.80
  5186.5 1273.12  5248.8 1276.18  5271.4 1277.29  5285.5 1278.83  5313.7 1279.13
#Mann=4,-1,0
  4429.2    0.05       0  5000.0    0.05       0  5005.0    0.05       0
  5248.8    0.12       0
Bank Sta=5000,5005
Exp/Cntr=0.3,0.1

Type RM Length L Ch R = 1,17622,477,477,477
BEGIN DESCRIPTION:
HICKORY37 35.0
END DESCRIPTION:
XS GIS Cut Line= 3
      2769450.28     10206334.68      2769283.00     10206752.00
      2769207.24     10207008.24
#Sta/Elev= 30
  4550.4 1275.89  4635.1 1275.85  4684.1 1274.96  4707.8 1273.97  4713.1 1273.06
  4737.4 1272.57  4742.7 1271.03  4820.1 1264.52  4828.8 1264.00  4839.6 1264.65
  4845.0 1263.63  4861.1 1265.09  4869.2 1265.22  4874.6 1264.37  4882.7 1264.89
  4893.4 1263.51  4904.2 1261.00  4943.9 1260.05  4952.6 1260.00  4979.5 1257.55
  4979.7 1257.50  4980.0 1257.00  4984.7 1257.50  5007.3 1258.78  5012.5 1260.33
  5046.6 1261.44  5112.3 1265.69  5117.5 1265.03  5147.8 1265.91  5267.2 1268.39
#Mann=9,-1,0
  4550.4    0.05       0  4684.1    0.12       0  4820.1    0.05       0
  4943.9    0.12       0  4979.5    0.05       0  4979.7    0.05       0
  4984.7    0.05       0  5046.6    0.12       0  5147.8    0.05       0
Bank Sta=4979.7,4984.7
Exp/Cntr=0.3,0.1

Type RM Length L Ch R = 1,17145,645,645,645
BEGIN DESCRIPTION:
HICKORY37 34.0
END DESCRIPTION:
XS GIS Cut Line= 3
      2768915.57     10206161.10      2768993.50     10206463.00
      2769213.58     10207179.98
#Sta/Elev= 30
  4688.2 1270.08  4741.9 1268.62  4845.2 1263.77  4979.5 1258.69  4986.7 1258.08
  4991.8 1256.62  5008.0 1255.83  5008.4 1255.33  5013.1 1255.83  5025.4 1258.65
  5083.8 1257.36  5104.7 1259.25  5123.6 1259.76  5136.1 1260.91  5156.3 1260.56
  5161.5 1261.51  5188.4 1261.79  5194.3 1262.68  5219.8 1263.76  5236.9 1265.27
  5264.9 1266.84  5292.4 1266.40  5297.7 1267.16  5330.4 1266.34  5341.1 1267.02
  5401.1 1267.82  5532.0 1266.83  5627.7 1268.77  5653.7 1270.37  5750.0 1274.91
#Mann=6,-1,0
  4688.2    0.05       0  5008.0    0.03       0  5013.1    0.05       0
  5236.9    0.12       0  5341.1    0.05       0  5653.7    0.12       0
Bank Sta=5008,5013.1
Exp/Cntr=0.3,0.1

Type RM Length L Ch R = 1,16500,500,500,500
BEGIN DESCRIPTION:
HICKORY37 33.0
END DESCRIPTION:
XS GIS Cut Line= 3
      2768405.71     10206803.13      2768738.80     10207004.63
      2769155.67     10207253.10
#Sta/Elev= 30
  4610.7 1267.74  4676.6 1265.50  4682.5 1264.32  4713.5 1263.53  4756.2 1260.27
  4854.9 1256.61  4909.4 1254.45  4928.6 1252.68  4952.1 1249.84  4983.1 1248.00
  5001.8 1245.41  5002.2 1244.91  5007.2 1245.41  5025.9 1249.66  5052.5 1251.24
  5095.2 1252.35  5121.3 1253.49  5127.1 1252.20  5136.1 1252.13  5216.7 1257.37
  5265.3 1261.72  5275.1 1261.69  5280.9 1263.06  5296.5 1261.67  5333.5 1263.67
  5391.9 1267.93  5406.2 1270.20  5427.1 1271.17  5462.0 1275.51  5485.3 1276.23
#Mann=8,-1,0
  4610.7    0.05       0  4854.9    0.12       0  4928.6    0.05       0
  5001.8    0.05       0  5007.2    0.05       0  5052.5    0.12       0
  5095.2    0.05       0  5406.2    0.12       0
Bank Sta=5001.8,5007.2
Exp/Cntr=0.3,0.1

Type RM Length L Ch R = 1,16000,500,500,500
BEGIN DESCRIPTION:
HICKORY37 32.0
END DESCRIPTION:
XS GIS Cut Line= 3
      2768305.68     10206803.10      2768346.77     10207291.47
      2768755.70     10207403.12
#Sta/Elev= 30
  4509.9 1266.79  4680.5 1258.72  4770.8 1250.09  4861.1 1247.22  4911.3 1244.07
  4921.4 1244.57  4958.8 1240.67  4959.2 1240.17  4963.8 1240.17  4964.2 1240.67
  4989.8 1241.50  5002.0 1241.69  5036.0 1244.58  5059.5 1245.71  5064.7 1246.66
  5071.4 1246.83  5081.8 1246.14  5099.2 1248.14  5104.4 1247.66  5123.3 1249.66
  5144.1 1253.10  5164.7 1253.98  5173.5 1253.51  5178.7 1254.25  5237.3 1256.80
  5268.4 1258.84  5287.5 1258.49  5361.7 1260.87  5372.1 1261.93  5423.9 1264.60
#Mann=5,-1,0
  4509.9    0.05       0  4958.8    0.07       0  4964.2    0.05       0
  4989.8    0.12       0  5036.0    0.05       0
Bank Sta=4958.8,4964.2
Exp/Cntr=0.3,0.1

Type RM Length L Ch R = 1,15500,500,500,500
BEGIN DESCRIPTION:
HICKORY37 31.0
END DESCRIPTION:
XS GIS Cut Line= 3
      2767805.65     10207403.08      2768028.59     10207594.12
      2768255.68     10208003.11
#Sta/Elev= 30
  4706.4 1254.79  4777.2 1253.24  4855.2 1248.88  4890.8 1243.77  4904.6 1242.63
  4926.5 1243.47  4961.6 1238.04  4969.3 1239.65  4975.9 1237.80  4983.0 1238.36
  4995.4 1235.92  5004.4 1236.82  5007.5 1235.79  5008.0 1235.29  5013.0 1235.79
  5020.5 1236.19  5026.2 1239.48  5069.7 1244.28  5107.4 1243.70  5129.1 1237.57
  5136.1 1236.89  5159.0 1240.55  5232.1 1241.07  5261.9 1243.69  5284.8 1244.17
  5297.3 1246.63  5313.3 1247.10  5364.9 1253.12  5422.1 1257.73  5467.8 1259.48
#Mann=3,-1,0
  4706.4    0.05       0  5007.5    0.05       0  5013.0    0.05       0
Bank Sta=5007.5,5013
Exp/Cntr=0.3,0.1

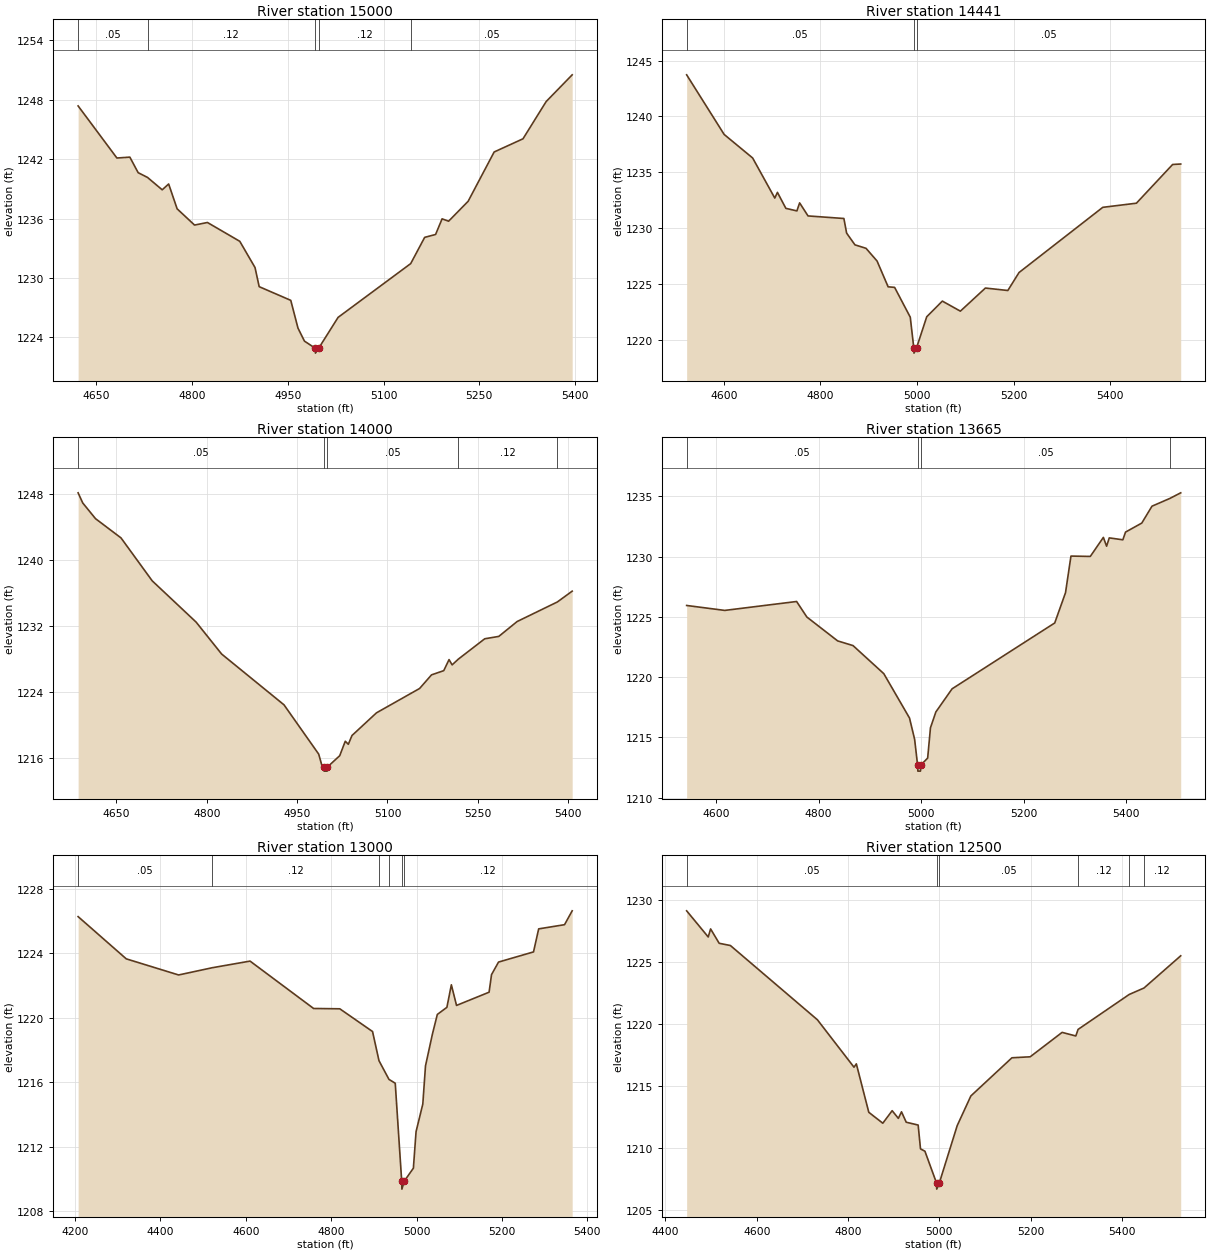
Type RM Length L Ch R = 1,15000,559,559,559
BEGIN DESCRIPTION:
HICKORY37 30.0
END DESCRIPTION:
XS GIS Cut Line= 3
      2767655.68     10207603.10      2767717.46     10207976.73
      2768105.72     10208053.12
#Sta/Elev= 30
  4621.3 1247.38  4682.1 1242.12  4702.4 1242.21  4715.4 1240.64  4730.1 1240.16
  4753.1 1238.91  4763.2 1239.50  4776.5 1236.99  4803.8 1235.35  4824.0 1235.61
  4874.7 1233.71  4898.6 1231.06  4905.1 1229.13  4954.6 1227.75  4965.9 1224.95
  4976.1 1223.63  4992.9 1222.92  4993.3 1222.42  4998.4 1222.92  5028.8 1226.03
  5142.6 1231.46  5164.5 1234.11  5181.6 1234.40  5191.8 1235.98  5202.0 1235.74
  5232.6 1237.75  5273.4 1242.73  5318.6 1244.06  5354.9 1247.82  5395.7 1250.52
#Mann=5,-1,0
  4621.3    0.05       0  4730.1    0.12       0  4992.9    0.07       0
  4998.4    0.12       0  5142.6    0.05       0
Bank Sta=4992.9,4998.4
Exp/Cntr=0.3,0.1

Type RM Length L Ch R = 1,14441,441,441,441
BEGIN DESCRIPTION:
HICKORY37 29.0
END DESCRIPTION:
XS GIS Cut Line= 3
      2766825.26     10208001.33      2767258.00     10208202.00
      2767755.86     10208424.96
#Sta/Elev= 30
  4523.0 1243.72  4600.6 1238.38  4659.6 1236.27  4705.4 1232.68  4710.9 1233.19
  4728.3 1231.76  4751.2 1231.53  4756.8 1232.25  4774.2 1231.08  4848.4 1230.85
  4854.1 1229.54  4871.3 1228.49  4894.2 1228.18  4917.1 1227.04  4940.0 1224.73
  4953.4 1224.68  4985.8 1222.01  4993.0 1219.29  4993.5 1218.79  4999.0 1219.29
  5019.9 1222.05  5052.2 1223.45  5089.5 1222.55  5141.3 1224.62  5187.7 1224.40
  5210.9 1226.01  5384.2 1231.85  5453.8 1232.22  5528.8 1235.69  5545.5 1235.73
#Mann=3,-1,0
  4523.0    0.05       0  4993.0    0.03       0  4999.0    0.05       0
Bank Sta=4993,4999
Exp/Cntr=0.3,0.1

Type RM Length L Ch R = 1,14000,335,335,335
BEGIN DESCRIPTION:
HICKORY37 28.0
END DESCRIPTION:
XS GIS Cut Line= 3
      2766905.64     10208403.09      2767255.27     10208624.05
      2767655.64     10208553.12
#Sta/Elev= 30
  4586.4 1248.12  4594.1 1246.89  4615.3 1244.99  4657.6 1242.66  4709.4 1237.46
  4782.3 1232.46  4824.7 1228.59  4928.2 1222.44  4985.8 1216.47  4991.7 1214.94
  4994.3 1214.91  4994.8 1214.41  4999.8 1214.41  5000.3 1214.91  5020.7 1216.28
  5029.9 1218.03  5035.0 1217.66  5041.0 1218.72  5081.7 1221.47  5153.3 1224.42
  5173.1 1226.07  5193.4 1226.58  5202.2 1227.92  5207.3 1227.28  5217.5 1227.97
  5261.4 1230.44  5284.8 1230.73  5315.2 1232.53  5382.0 1234.90  5406.6 1236.21
#Mann=5,-1,0
  4586.4    0.05       0  4994.3    0.03       0  5000.3    0.05       0
  5217.5    0.12       0  5382.0    0.05       0
Bank Sta=4994.3,5000.3
Exp/Cntr=0.3,0.1

Type RM Length L Ch R = 1,13665,665,665,665
BEGIN DESCRIPTION:
HICKORY37 27.0
END DESCRIPTION:
XS GIS Cut Line= 3
      2766811.43     10208966.62      2767268.50     10208952.00
      2767748.87     10208793.01
#Sta/Elev= 30
  4542.7 1225.94  4617.0 1225.53  4757.1 1226.27  4777.1 1224.98  4837.1 1223.00
  4867.1 1222.61  4927.1 1220.28  4977.2 1216.60  4987.2 1214.83  4993.0 1212.69
  4993.5 1212.19  4998.6 1212.19  4999.1 1212.69  5012.6 1213.27  5018.1 1215.79
  5028.6 1217.10  5060.2 1219.02  5260.4 1224.49  5281.4 1227.00  5292.0 1230.04
  5329.7 1230.01  5355.2 1231.59  5361.5 1230.86  5366.7 1231.55  5393.2 1231.39
  5398.4 1232.03  5430.1 1232.78  5450.0 1234.18  5485.1 1234.83  5506.0 1235.29
#Mann=4,-1,0
  4542.7    0.05       0  4993.0    0.05       0  4999.1    0.05       0
  5485.1    0.12       0
Bank Sta=4993,4999.1
Exp/Cntr=0.3,0.1

Type RM Length L Ch R = 1,13000,500,500,500
BEGIN DESCRIPTION:
HICKORY37 26.0
END DESCRIPTION:
XS GIS Cut Line= 3
      2766776.65     10209029.11      2767522.63     10209298.13
      2767846.08     10209466.60
#Sta/Elev= 30
  4207.0 1226.28  4319.8 1223.66  4442.5 1222.66  4521.6 1223.11  4609.9 1223.52
  4758.8 1220.58  4820.2 1220.56  4896.9 1219.15  4912.0 1217.34  4935.4 1216.18
  4950.1 1215.94  4965.2 1209.87  4965.7 1209.37  4971.4 1209.87  4992.6 1210.67
  4998.9 1212.94  5014.7 1214.65  5021.0 1217.02  5037.3 1219.00  5048.7 1220.21
  5071.1 1220.65  5081.6 1222.05  5093.7 1220.77  5170.0 1221.59  5175.7 1222.68
  5192.1 1223.46  5274.1 1224.09  5286.2 1225.52  5346.8 1225.78  5364.7 1226.64
#Mann=6,-1,0
  4207.0    0.05       0  4521.6    0.12       0  4912.0    0.05       0
  4935.4    0.12       0  4965.2    0.07       0  4971.4    0.12       0
Bank Sta=4965.2,4971.4
Exp/Cntr=0.3,0.1

Type RM Length L Ch R = 1,12500,500,500,500
BEGIN DESCRIPTION:
HICKORY37 25.0
END DESCRIPTION:
XS GIS Cut Line= 3
      2766596.07     10209487.44      2767136.38     10209608.04
      2767665.57     10209605.51
#Sta/Elev= 30
  4446.4 1229.16  4493.7 1227.05  4498.9 1227.70  4517.7 1226.54  4542.3 1226.36
  4732.9 1220.37  4813.2 1216.54  4818.3 1216.81  4845.6 1212.90  4876.3 1212.02
  4896.8 1213.03  4910.4 1212.41  4917.3 1212.94  4927.6 1212.10  4953.8 1211.87
  4958.9 1209.95  4968.6 1209.76  4994.0 1207.20  4994.5 1206.70  5000.2 1207.20
  5039.3 1211.82  5069.3 1214.22  5159.3 1217.30  5199.3 1217.38  5269.3 1219.35
  5299.3 1219.06  5304.3 1219.59  5416.3 1222.41  5448.7 1222.93  5529.2 1225.53
#Mann=6,-1,0
  4446.4    0.05       0  4994.0    0.03       0  5000.2    0.05       0
  5304.3    0.12       0  5416.3    0.05       0  5448.7    0.12       0
Bank Sta=4994,5000.2
Exp/Cntr=0.3,0.1

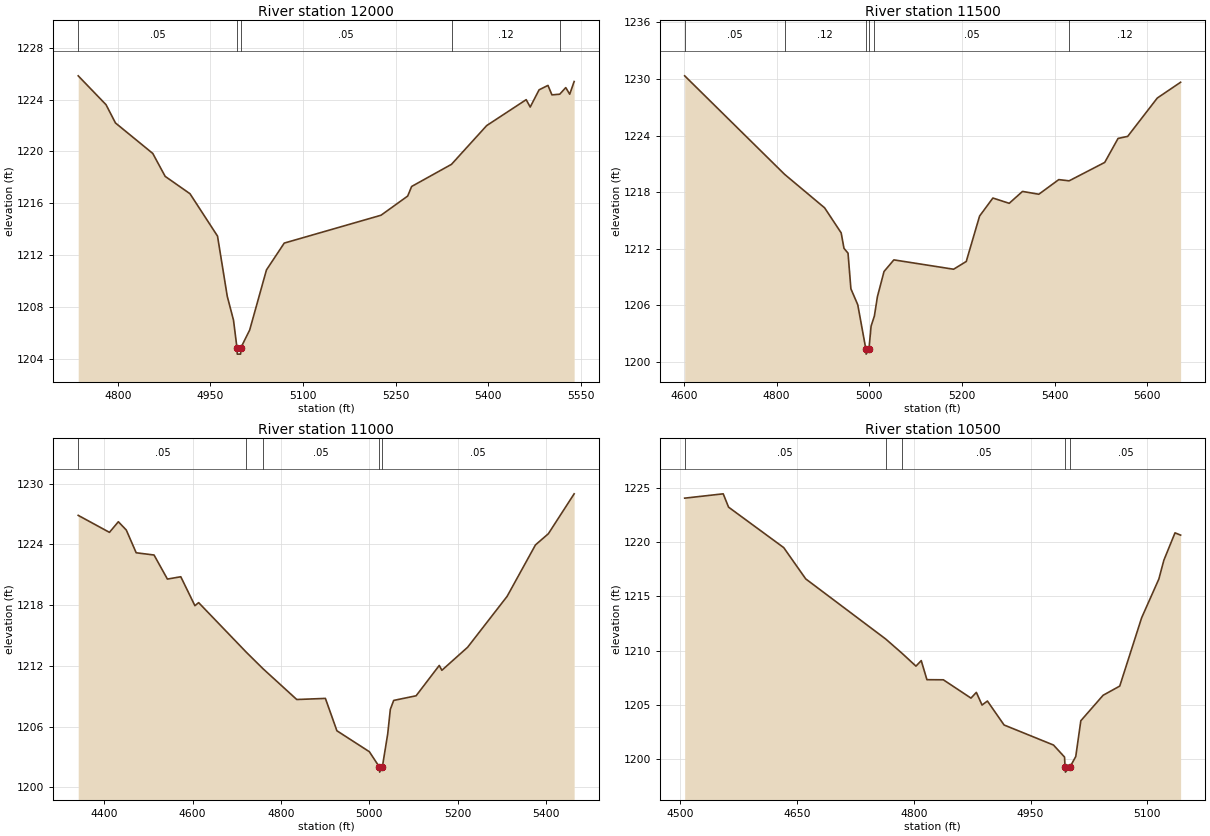
Type RM Length L Ch R = 1,12000,500,500,500
BEGIN DESCRIPTION:
HICKORY37 24.0
END DESCRIPTION:
XS GIS Cut Line= 3
      2767155.68     10210253.13      2767185.06     10209990.57
      2767605.71     10209653.09
#Sta/Elev= 30
  4735.8 1225.83  4780.9 1223.60  4796.2 1222.19  4856.6 1219.84  4876.7 1218.07
  4916.9 1216.73  4961.5 1213.46  4977.3 1208.81  4987.4 1206.97  4993.0 1204.85
  4993.5 1204.35  4998.9 1204.35  4999.4 1204.85  5013.6 1206.21  5040.8 1210.85
  5069.6 1212.92  5226.4 1215.07  5269.6 1216.55  5276.0 1217.29  5340.6 1219.00
  5397.6 1221.99  5461.6 1223.99  5468.1 1223.42  5482.5 1224.75  5496.9 1225.09
  5503.3 1224.36  5515.9 1224.41  5525.7 1224.92  5532.1 1224.41  5539.3 1225.39
#Mann=5,-1,0
  4735.8    0.05       0  4993.0    0.05       0  4999.4    0.05       0
  5340.6    0.12       0  5515.9    0.05       0
Bank Sta=4993,4999.4
Exp/Cntr=0.3,0.1

Type RM Length L Ch R = 1,11500,500,500,500
BEGIN DESCRIPTION:
HICKORY37 23.0
END DESCRIPTION:
XS GIS Cut Line= 3
      2767305.68     10210403.12      2767631.65     10210174.41
      2768055.69     10209653.10
#Sta/Elev= 30
  4601.8 1230.32  4817.4 1219.89  4903.8 1216.34  4939.5 1213.69  4945.6 1212.05
  4954.3 1211.54  4960.5 1207.77  4975.3 1206.08  4992.9 1201.35  4993.4 1200.85
  4999.4 1201.35  5004.1 1203.82  5011.2 1204.89  5017.7 1206.93  5032.0 1209.60
  5053.2 1210.83  5182.1 1209.84  5209.4 1210.66  5238.2 1215.47  5266.9 1217.38
  5302.1 1216.82  5330.8 1218.08  5366.0 1217.78  5409.1 1219.33  5431.4 1219.20
  5508.2 1221.15  5537.0 1223.69  5557.8 1223.91  5621.7 1227.97  5672.0 1229.64
#Mann=6,-1,0
  4601.8    0.05       0  4817.4    0.12       0  4992.9    0.07       0
  4999.4    0.12       0  5011.2    0.05       0  5431.4    0.12       0
Bank Sta=4992.9,4999.4
Exp/Cntr=0.3,0.1

Type RM Length L Ch R = 1,11000,500,500,500
BEGIN DESCRIPTION:
HICKORY37 22.0
END DESCRIPTION:
XS GIS Cut Line= 3
      2767405.67     10210403.11      2768058.40     10210314.65
      2768455.72     10210553.13
#Sta/Elev= 30
  4341.3 1226.88  4412.0 1225.20  4432.1 1226.25  4450.1 1225.43  4472.5 1223.18
  4512.9 1222.96  4543.1 1220.58  4573.4 1220.81  4605.3 1217.95  4613.8 1218.25
  4722.0 1213.33  4759.8 1211.70  4835.8 1208.67  4900.6 1208.78  4926.6 1205.58
  5000.0 1203.51  5022.8 1201.99  5023.3 1201.49  5029.4 1201.99  5041.6 1205.28
  5047.5 1207.70  5055.1 1208.58  5105.8 1209.04  5158.2 1212.04  5164.1 1211.56
  5222.4 1213.84  5311.7 1218.87  5375.9 1223.96  5405.0 1225.06  5463.4 1229.01
#Mann=5,-1,0
  4341.3    0.05       0  4722.0    0.12       0  4759.8    0.05       0
  5022.8    0.05       0  5029.4    0.05       0
Bank Sta=5022.8,5029.4
Exp/Cntr=0.3,0.1

Type RM Length L Ch R = 1,10500,500,500,500
BEGIN DESCRIPTION:
HICKORY37 21.0
END DESCRIPTION:
XS GIS Cut Line= 3
      2767555.72     10210403.15      2767896.14     10210761.68
      2768005.69     10210853.12
#Sta/Elev= 30
  4505.6 1224.07  4555.1 1224.47  4562.0 1223.24  4632.8 1219.51  4661.1 1216.62
  4763.9 1211.07  4784.6 1209.77  4802.7 1208.57  4809.5 1209.08  4816.8 1207.32
  4837.9 1207.31  4873.4 1205.62  4880.3 1206.15  4887.6 1204.98  4894.5 1205.35
  4915.9 1203.14  4979.4 1201.29  4993.6 1200.18  4994.2 1199.29  4994.7 1198.79
  5000.8 1199.29  5008.0 1200.23  5014.5 1203.53  5043.1 1205.88  5064.5 1206.73
  5092.6 1213.03  5114.7 1216.60  5121.2 1218.35  5135.5 1220.87  5142.7 1220.66
#Mann=5,-1,0
  4505.6    0.05       0  4763.9    0.12       0  4784.6    0.05       0
  4994.2    0.05       0  5000.8    0.05       0
Bank Sta=4994.2,5000.8
Exp/Cntr=0.3,0.1