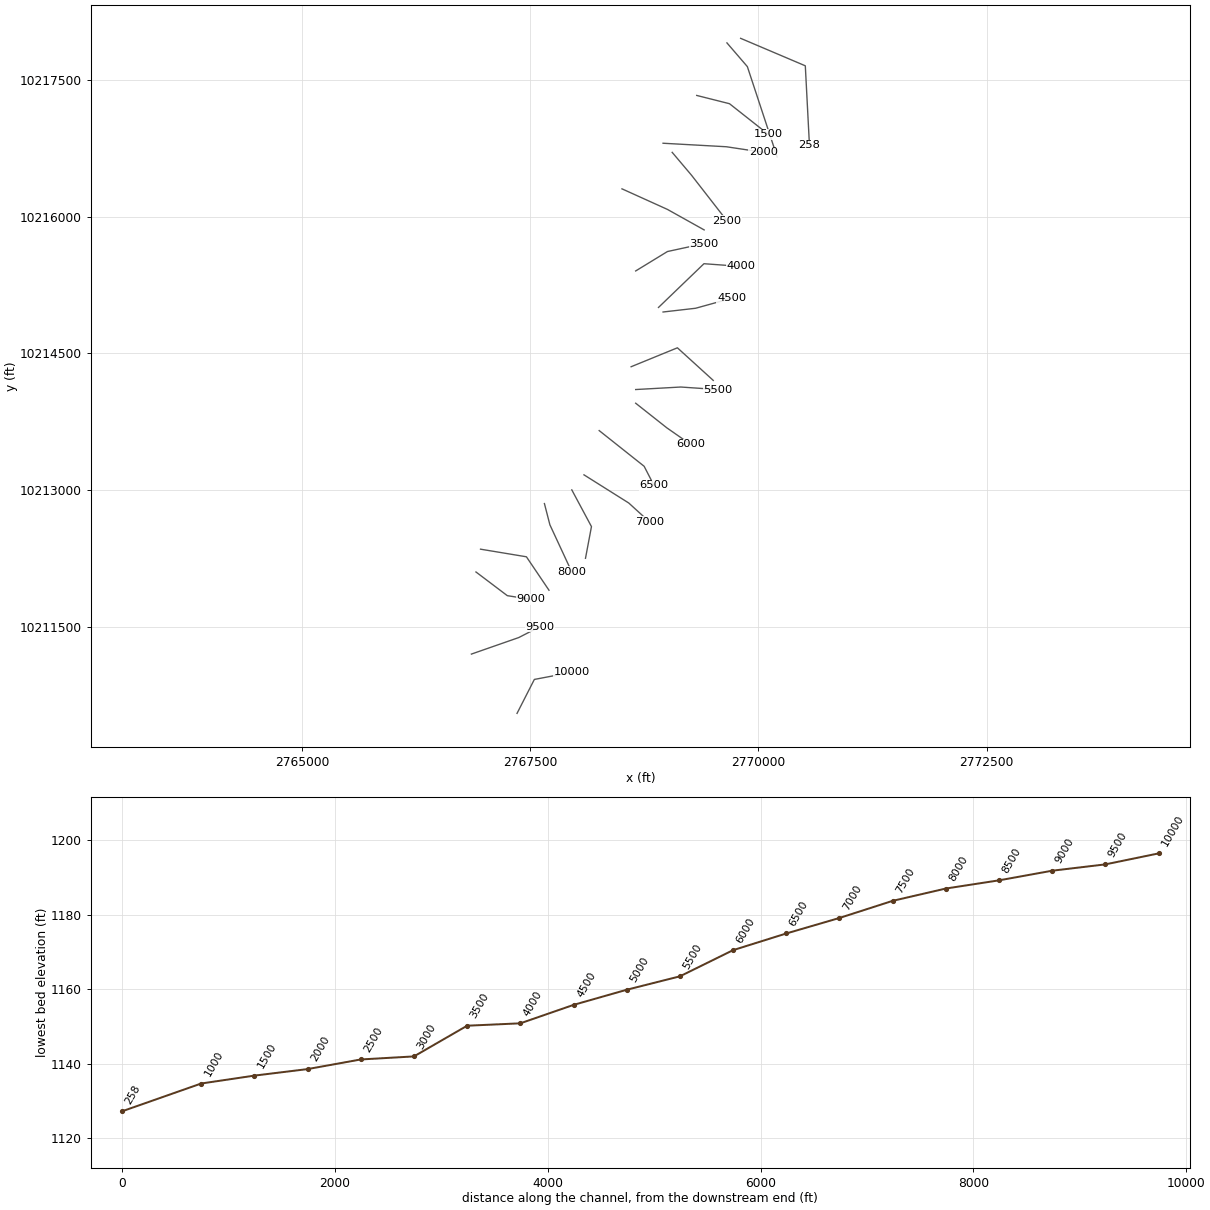
HEC-RAS study HICKORY37.prj: HICKORY37 Base Level Engineering

--- HICKORY37.g01 (geometry) --- (continued)

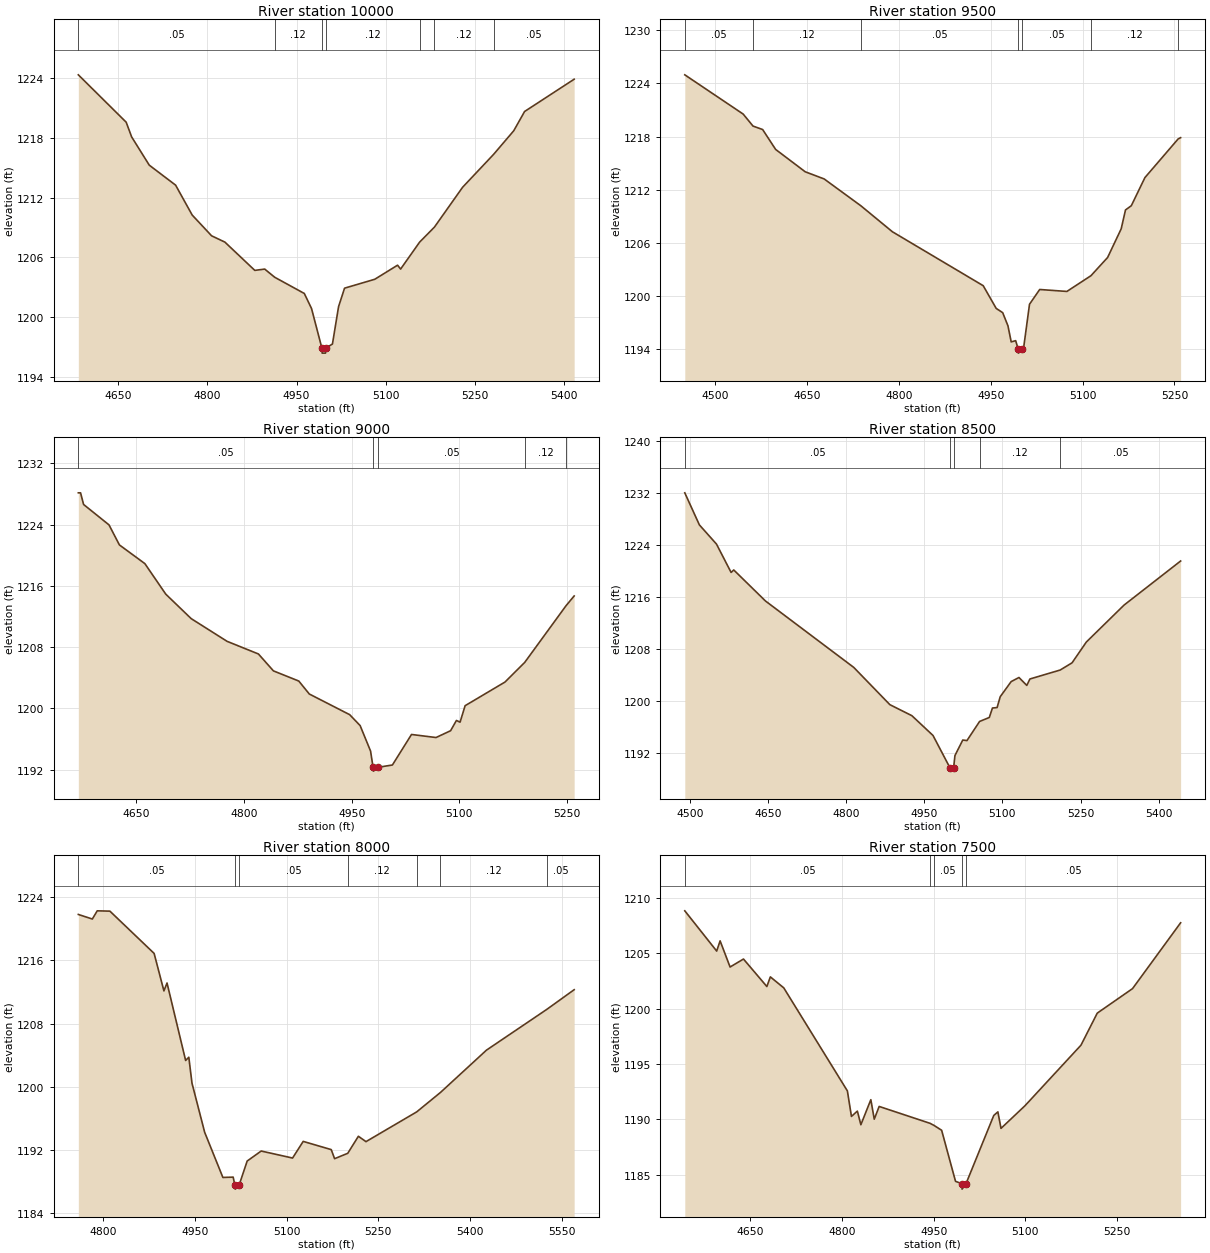
Type RM Length L Ch R = 1,10000,500,500,500
BEGIN DESCRIPTION:
HICKORY37 20.0
END DESCRIPTION:
XS GIS Cut Line= 3
      2767355.68     10210553.11      2767545.35     10210925.15
      2767955.71     10211003.12
#Sta/Elev= 30
  4582.4 1224.28  4663.0 1219.54  4672.2 1218.07  4701.9 1215.24  4746.3 1213.24
  4774.2 1210.25  4806.9 1208.17  4829.3 1207.54  4879.7 1204.71  4896.4 1204.84
  4913.3 1204.02  4963.1 1202.40  4975.3 1200.89  4992.7 1196.93  4993.2 1196.43
  4998.8 1196.43  4999.3 1196.93  5010.5 1197.34  5020.8 1201.08  5030.9 1202.93
  5081.8 1203.82  5120.2 1205.23  5125.3 1204.84  5157.4 1207.54  5182.3 1209.04
  5229.8 1213.03  5282.0 1216.32  5315.9 1218.68  5334.2 1220.61  5417.7 1223.84
#Mann=7,-1,0
  4582.4    0.05       0  4913.3    0.12       0  4992.7    0.07       0
  4999.3    0.12       0  5157.4    0.05       0  5182.3    0.12       0
  5282.0    0.05       0
Bank Sta=4992.7,4999.3
Exp/Cntr=0.3,0.1

Type RM Length L Ch R = 1,9500,500,500,500
BEGIN DESCRIPTION:
HICKORY37 19.0
END DESCRIPTION:
XS GIS Cut Line= 3
      2766855.68     10211203.11      2767374.46     10211384.26
      2767605.70     10211503.12
#Sta/Elev= 30
  4450.5 1224.98  4545.8 1220.54  4561.9 1219.18  4577.6 1218.79  4598.8 1216.54
  4647.1 1214.01  4678.0 1213.20  4738.0 1210.16  4789.5 1207.22  4937.7 1201.12
  4958.9 1198.55  4969.5 1198.07  4978.1 1196.58  4983.4 1194.76  4990.7 1194.90
  4994.6 1193.99  4995.1 1193.49  5001.4 1193.99  5003.5 1193.99  5013.3 1199.02
  5029.9 1200.69  5074.3 1200.47  5113.6 1202.25  5140.8 1204.31  5163.0 1207.56
  5170.0 1209.69  5179.5 1210.17  5201.7 1213.35  5256.0 1217.73  5260.0 1217.87
#Mann=7,-1,0
  4450.5    0.05       0  4561.9    0.12       0  4738.0    0.05       0
  4994.6    0.05       0  5001.4    0.05       0  5113.6    0.12       0
  5256.0    0.05       0
Bank Sta=4994.6,5001.4
Exp/Cntr=0.3,0.1

Type RM Length L Ch R = 1,9000,500,500,500
BEGIN DESCRIPTION:
HICKORY37 18.0
END DESCRIPTION:
XS GIS Cut Line= 3
      2766905.69     10212103.11      2767249.09     10211843.49
      2767505.64     10211803.12
#Sta/Elev= 30
  4569.5 1228.16  4572.6 1228.16  4576.8 1226.64  4612.2 1223.97  4626.7 1221.35
  4662.1 1218.91  4691.2 1214.92  4726.6 1211.72  4776.6 1208.75  4820.2 1207.10
  4841.1 1204.89  4876.4 1203.56  4891.0 1201.87  4947.2 1199.17  4961.8 1197.74
  4976.3 1194.41  4979.8 1192.29  4980.3 1191.79  4986.6 1192.29  5006.7 1192.59
  5033.3 1196.58  5067.4 1196.18  5087.7 1197.07  5095.8 1198.41  5100.9 1198.19
  5107.9 1200.34  5163.4 1203.43  5190.9 1206.00  5248.5 1213.42  5259.7 1214.68
#Mann=5,-1,0
  4569.5    0.05       0  4979.8    0.05       0  4986.6    0.05       0
  5190.9    0.12       0  5248.5    0.05       0
Bank Sta=4979.8,4986.6
Exp/Cntr=0.3,0.1

Type RM Length L Ch R = 1,8500,500,500,500
BEGIN DESCRIPTION:
HICKORY37 17.0
END DESCRIPTION:
XS GIS Cut Line= 3
      2766955.67     10212353.11      2767458.38     10212269.64
      2767705.71     10211903.07
#Sta/Elev= 30
  4490.4 1232.07  4518.4 1227.13  4551.2 1224.18  4579.3 1219.81  4584.4 1220.19
  4645.3 1215.41  4814.8 1205.18  4884.0 1199.45  4926.3 1197.75  4966.9 1194.70
  4999.5 1189.71  5000.0 1189.21  5006.4 1189.71  5009.0 1191.61  5024.0 1194.00
  5032.0 1193.91  5056.3 1196.86  5074.9 1197.47  5081.0 1198.93  5089.9 1199.00
  5095.9 1200.67  5116.9 1203.00  5131.9 1203.63  5146.9 1202.41  5152.9 1203.40
  5211.0 1204.78  5233.8 1205.89  5261.2 1209.09  5333.6 1214.78  5442.2 1221.57
#Mann=5,-1,0
  4490.4    0.05       0  4999.5    0.03       0  5006.4    0.05       0
  5056.3    0.12       0  5211.0    0.05       0
Bank Sta=4999.5,5006.4
Exp/Cntr=0.3,0.1

Type RM Length L Ch R = 1,8000,500,500,500
BEGIN DESCRIPTION:
HICKORY37 16.0
END DESCRIPTION:
XS GIS Cut Line= 3
      2767655.69     10212853.07      2767715.60     10212620.36
      2767955.66     10212103.16
#Sta/Elev= 30
  4759.7 1221.83  4782.6 1221.25  4790.6 1222.29  4811.3 1222.25  4883.6 1216.89
  4899.6 1212.14  4904.7 1213.14  4935.1 1203.32  4940.3 1203.73  4945.5 1200.44
  4966.2 1194.22  4996.0 1188.49  5012.8 1188.53  5015.6 1187.51  5016.1 1187.01
  5022.5 1187.51  5035.7 1190.57  5058.6 1191.84  5109.9 1190.95  5127.3 1193.06
  5173.1 1192.02  5178.6 1190.87  5200.1 1191.55  5217.5 1193.71  5229.9 1193.03
  5312.8 1196.80  5351.6 1199.26  5426.9 1204.63  5525.2 1209.78  5570.2 1212.29
#Mann=7,-1,0
  4759.7    0.05       0  5015.6    0.05       0  5022.5    0.05       0
  5200.1    0.12       0  5312.8    0.05       0  5351.6    0.12       0
  5525.2    0.05       0
Bank Sta=5015.6,5022.5
Exp/Cntr=0.3,0.1

Type RM Length L Ch R = 1,7500,500,500,500
BEGIN DESCRIPTION:
HICKORY37 15.0
END DESCRIPTION:
XS GIS Cut Line= 3
      2767955.66     10213003.15      2768171.17     10212600.61
      2768105.69     10212253.13
#Sta/Elev= 30
  4543.4 1208.82  4595.5 1205.19  4601.1 1206.11  4617.4 1203.75  4639.3 1204.47
  4677.5 1201.99  4683.2 1202.86  4705.1 1201.87  4809.1 1192.57  4815.7 1190.27
  4825.4 1190.75  4831.1 1189.52  4847.4 1191.78  4853.0 1190.02  4861.0 1191.17
  4944.0 1189.65  4950.3 1189.47  4963.1 1189.02  4985.8 1184.41  4996.0 1184.21
  4996.5 1183.71  5003.0 1184.21  5048.3 1190.36  5055.0 1190.68  5060.1 1189.19
  5099.2 1191.23  5190.8 1196.70  5217.4 1199.59  5275.0 1201.80  5353.6 1207.74
#Mann=5,-1,0
  4543.4    0.05       0  4944.0    0.12       0  4950.3    0.05       0
  4996.0    0.05       0  5003.0    0.05       0
Bank Sta=4996,5003
Exp/Cntr=0.3,0.1

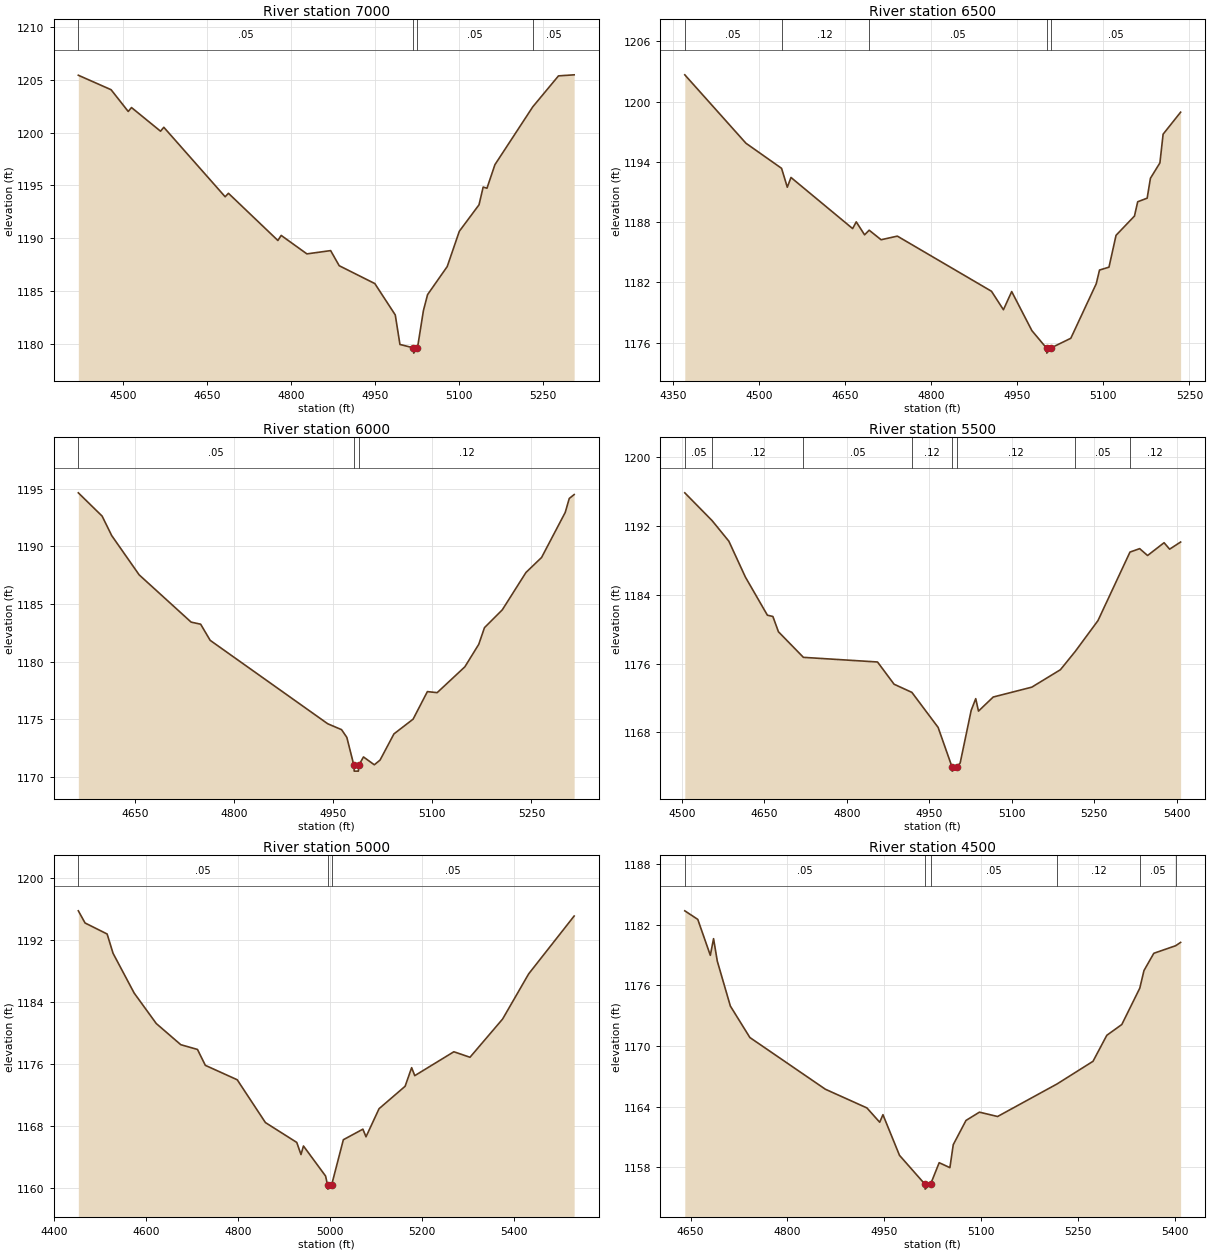
Type RM Length L Ch R = 1,7000,500,500,500
BEGIN DESCRIPTION:
HICKORY37 14.0
END DESCRIPTION:
XS GIS Cut Line= 3
      2768089.15     10213168.02      2768579.91     10212859.08
      2768805.68     10212653.12
#Sta/Elev= 30
  4420.1 1205.44  4478.6 1204.07  4509.2 1202.01  4515.1 1202.38  4566.9 1200.14
  4572.8 1200.51  4682.3 1193.93  4688.2 1194.26  4776.5 1189.79  4782.4 1190.27
  4828.3 1188.52  4870.7 1188.83  4886.0 1187.40  4949.6 1185.71  4986.1 1182.74
  4994.5 1179.94  5018.6 1179.62  5019.1 1179.12  5025.8 1179.62  5036.4 1183.15
  5043.8 1184.66  5078.9 1187.32  5100.5 1190.66  5135.7 1193.17  5143.1 1194.85
  5149.9 1194.74  5164.1 1196.97  5231.7 1202.45  5277.6 1205.38  5305.6 1205.48
#Mann=4,-1,0
  4420.1    0.05       0  5018.6    0.05       0  5025.8    0.05       0
  5231.7    0.05       0
Bank Sta=5018.6,5025.8
Exp/Cntr=0.3,0.1

Type RM Length L Ch R = 1,6500,500,500,500
BEGIN DESCRIPTION:
HICKORY37 13.0
END DESCRIPTION:
XS GIS Cut Line= 3
      2768255.71     10213653.09      2768748.33     10213261.81
      2768855.69     10213053.11
#Sta/Elev= 30
  4370.9 1202.67  4477.4 1195.86  4539.5 1193.36  4549.5 1191.48  4555.9 1192.45
  4663.3 1187.36  4669.6 1188.03  4684.1 1186.74  4692.1 1187.20  4712.9 1186.25
  4741.2 1186.61  4905.2 1181.12  4926.0 1179.28  4940.4 1181.09  4975.6 1177.20
  5001.1 1175.46  5001.6 1174.96  5008.3 1175.46  5043.4 1176.44  5087.7 1181.87
  5093.4 1183.23  5109.9 1183.52  5122.2 1186.69  5154.3 1188.61  5159.9 1190.03
  5176.4 1190.39  5182.1 1192.37  5198.6 1193.90  5204.2 1196.76  5234.7 1198.95
#Mann=5,-1,0
  4370.9    0.05       0  4539.5    0.12       0  4692.1    0.05       0
  5001.1    0.03       0  5008.3    0.05       0
Bank Sta=5001.1,5008.3
Exp/Cntr=0.3,0.1

Type RM Length L Ch R = 1,6000,500,500,500
BEGIN DESCRIPTION:
HICKORY37 12.0
END DESCRIPTION:
XS GIS Cut Line= 3
      2768655.72     10213953.09      2768997.49     10213682.85
      2769255.69     10213503.11
#Sta/Elev= 30
  4564.3 1194.64  4600.3 1192.62  4614.8 1190.93  4656.4 1187.52  4735.0 1183.42
  4749.4 1183.24  4763.8 1181.84  4941.7 1174.60  4962.6 1174.09  4970.6 1173.42
  4981.3 1170.99  4981.8 1170.49  4988.1 1170.49  4988.6 1170.99  4995.8 1171.72
  5012.2 1171.04  5020.9 1171.45  5041.9 1173.72  5070.9 1175.00  5092.5 1177.39
  5107.3 1177.30  5149.2 1179.54  5170.2 1181.49  5178.9 1182.94  5205.9 1184.49
  5241.7 1187.73  5265.3 1189.03  5301.1 1192.94  5307.2 1194.15  5314.6 1194.49
#Mann=3,-1,0
  4564.3    0.05       0  4981.3    0.07       0  4988.6    0.12       0
Bank Sta=4981.3,4988.6
Exp/Cntr=0.3,0.1

Type RM Length L Ch R = 1,5500,500,500,500
BEGIN DESCRIPTION:
HICKORY37 11.0
END DESCRIPTION:
XS GIS Cut Line= 3
      2768655.69     10214103.11      2769149.52     10214130.66
      2769555.68     10214103.11
#Sta/Elev= 30
  4505.4 1195.88  4555.1 1192.64  4585.5 1190.25  4615.6 1186.07  4655.6 1181.63
  4665.6 1181.48  4675.7 1179.70  4721.1 1176.72  4855.9 1176.18  4886.0 1173.59
  4918.4 1172.64  4966.1 1168.56  4991.3 1163.97  4991.8 1163.47  4999.9 1163.97
  5006.2 1164.42  5026.2 1170.54  5034.5 1171.91  5039.5 1170.46  5066.3 1172.10
  5136.5 1173.25  5188.5 1175.28  5215.7 1177.43  5256.8 1181.00  5315.0 1188.98
  5332.6 1189.38  5347.0 1188.58  5377.0 1190.07  5387.1 1189.32  5407.1 1190.15
#Mann=8,-1,0
  4505.4    0.05       0  4555.1    0.12       0  4721.1    0.05       0
  4918.4    0.12       0  4991.3    0.07       0  4999.9    0.12       0
  5215.7    0.05       0  5315.0    0.12       0
Bank Sta=4991.3,4999.9
Exp/Cntr=0.3,0.1

Type RM Length L Ch R = 1,5000,500,500,500
BEGIN DESCRIPTION:
HICKORY37 10.0
END DESCRIPTION:
XS GIS Cut Line= 3
      2768605.67     10214353.11      2769112.75     10214560.63
      2769505.66     10214203.14
#Sta/Elev= 30
  4452.1 1195.75  4466.8 1194.18  4514.8 1192.76  4527.7 1190.27  4573.6 1185.15
  4621.7 1181.22  4675.1 1178.49  4711.4 1177.88  4728.5 1175.83  4797.9 1173.97
  4859.3 1168.45  4927.5 1165.89  4936.7 1164.33  4942.1 1165.43  4990.2 1161.56
  4994.6 1160.37  4995.1 1159.87  5003.2 1160.37  5028.9 1166.24  5071.4 1167.60
  5078.2 1166.62  5106.6 1170.24  5163.3 1173.13  5177.5 1175.53  5184.3 1174.50
  5269.4 1177.58  5304.5 1176.87  5375.5 1181.80  5432.2 1187.62  5531.2 1195.08
#Mann=3,-1,0
  4452.1    0.05       0  4994.6    0.05       0  5003.2    0.05       0
Bank Sta=4994.6,5003.2
Exp/Cntr=0.3,0.1

Type RM Length L Ch R = 1,4500,500,500,500
BEGIN DESCRIPTION:
HICKORY37 9.0
END DESCRIPTION:
XS GIS Cut Line= 3
      2768955.69     10214953.11      2769312.24     10214994.13
      2769705.72     10215103.12
#Sta/Elev= 30
  4641.1 1183.40  4661.2 1182.55  4680.6 1178.99  4685.6 1180.64  4691.4 1178.41
  4711.6 1173.96  4741.8 1170.84  4858.7 1165.71  4922.9 1163.86  4942.7 1162.44
  4947.7 1163.19  4973.3 1159.16  5012.5 1156.31  5013.0 1155.81  5021.5 1156.31
  5034.7 1158.43  5051.3 1157.94  5056.5 1160.22  5076.2 1162.62  5097.0 1163.44
  5125.1 1163.01  5217.2 1166.24  5272.7 1168.48  5294.1 1171.06  5317.3 1172.13
  5345.1 1175.73  5351.6 1177.48  5366.8 1179.19  5400.6 1179.94  5408.3 1180.27
#Mann=6,-1,0
  4641.1    0.05       0  5012.5    0.05       0  5021.5    0.05       0
  5217.2    0.12       0  5345.1    0.05       0  5400.6    0.12       0
Bank Sta=5012.5,5021.5
Exp/Cntr=0.3,0.1

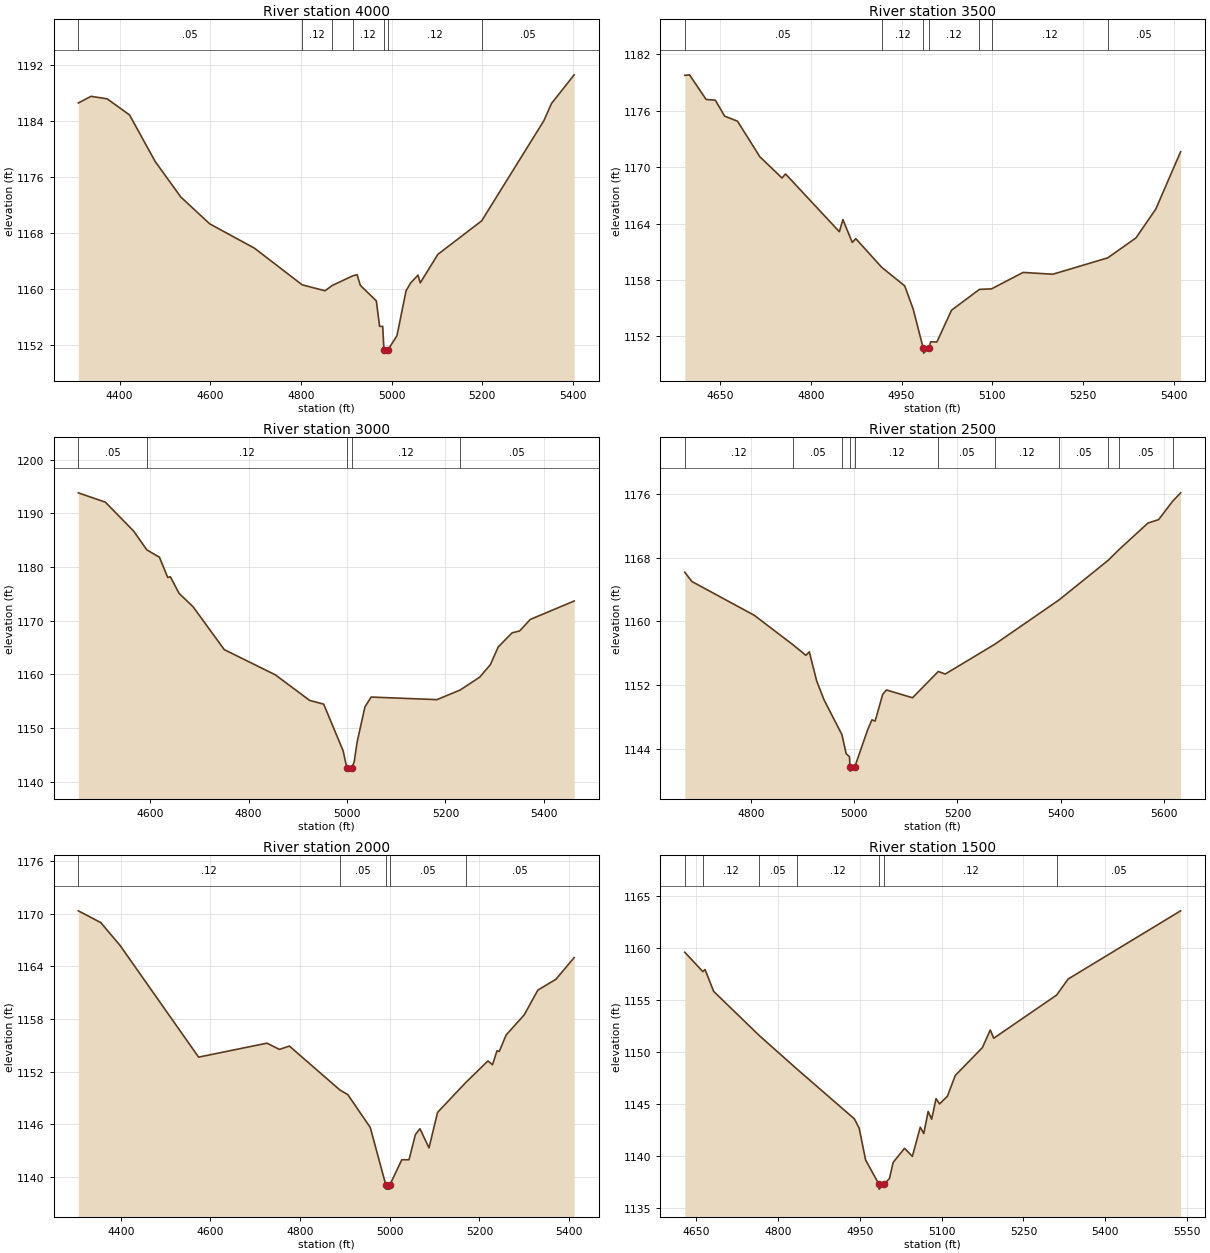
Type RM Length L Ch R = 1,4000,500,500,500
BEGIN DESCRIPTION:
HICKORY37 8.0
END DESCRIPTION:
XS GIS Cut Line= 3
      2768905.70     10215003.13      2769403.69     10215482.47
      2769805.72     10215453.11
#Sta/Elev= 30
  4308.8 1186.61  4336.9 1187.56  4372.5 1187.20  4421.8 1184.90  4478.4 1178.25
  4535.0 1173.17  4598.8 1169.34  4697.6 1165.86  4802.8 1160.63  4853.3 1159.78
  4869.0 1160.53  4914.4 1161.91  4924.0 1162.08  4931.2 1160.55  4966.5 1158.34
  4973.7 1154.70  4980.6 1154.69  4983.3 1151.37  4983.8 1150.87  4992.4 1151.37
  5012.0 1153.35  5032.1 1159.77  5042.1 1160.89  5058.5 1162.02  5063.5 1160.91
  5102.3 1164.98  5199.0 1169.77  5336.2 1184.07  5352.9 1186.52  5403.1 1190.63
#Mann=7,-1,0
  4308.8    0.05       0  4802.8    0.12       0  4869.0    0.05       0
  4914.4    0.12       0  4983.3    0.07       0  4992.4    0.12       0
  5199.0    0.05       0
Bank Sta=4983.3,4992.4
Exp/Cntr=0.3,0.1

Type RM Length L Ch R = 1,3500,500,500,500
BEGIN DESCRIPTION:
HICKORY37 7.0
END DESCRIPTION:
XS GIS Cut Line= 3
      2768655.66     10215403.10      2769003.79     10215616.05
      2769405.67     10215703.11
#Sta/Elev= 30
  4591.9 1179.76  4599.7 1179.82  4627.1 1177.20  4642.3 1177.13  4657.7 1175.43
  4679.0 1174.89  4715.8 1171.12  4752.5 1168.85  4758.4 1169.28  4847.3 1163.14
  4853.2 1164.43  4868.6 1162.00  4874.5 1162.40  4917.2 1159.36  4955.3 1157.38
  4969.3 1154.91  4986.0 1150.73  4986.5 1150.23  4995.1 1150.73  4998.2 1151.44
  5008.4 1151.41  5032.6 1154.79  5078.8 1157.01  5098.7 1157.06  5150.9 1158.81
  5200.1 1158.62  5290.8 1160.36  5337.4 1162.48  5370.3 1165.56  5411.2 1171.65
#Mann=7,-1,0
  4591.9    0.05       0  4917.2    0.12       0  4986.0    0.07       0
  4995.1    0.12       0  5078.8    0.05       0  5098.7    0.12       0
  5290.8    0.05       0
Bank Sta=4986,4995.1
Exp/Cntr=0.3,0.1

Type RM Length L Ch R = 1,3000,500,500,500
BEGIN DESCRIPTION:
HICKORY37 6.0
END DESCRIPTION:
XS GIS Cut Line= 3
      2768505.65     10216303.13      2769002.90     10216078.10
      2769405.72     10215853.09
#Sta/Elev= 30
  4454.2 1193.81  4509.1 1192.07  4566.4 1186.71  4593.5 1183.18  4618.9 1181.83
  4635.8 1178.06  4641.2 1178.17  4658.9 1175.09  4687.4 1172.59  4750.6 1164.62
  4854.7 1159.91  4924.0 1155.17  4952.6 1154.47  4992.1 1145.78  4999.9 1142.50
  5000.4 1142.00  5009.1 1142.50  5014.6 1143.74  5020.4 1147.36  5036.4 1153.95
  5049.0 1155.79  5182.6 1155.31  5229.6 1157.09  5269.5 1159.49  5291.2 1161.83
  5307.2 1165.12  5335.4 1167.75  5350.6 1168.09  5372.3 1170.24  5461.4 1173.67
#Mann=5,-1,0
  4454.2    0.05       0  4593.5    0.12       0  4999.9    0.07       0
  5009.1    0.12       0  5229.6    0.05       0
Bank Sta=4999.9,5009.1
Exp/Cntr=0.3,0.1

Type RM Length L Ch R = 1,2500,500,500,500
BEGIN DESCRIPTION:
HICKORY37 5.0
END DESCRIPTION:
XS GIS Cut Line= 3
      2769055.70     10216703.09      2769267.48     10216452.36
      2769655.68     10215953.12
#Sta/Elev= 30
  4671.8 1166.17  4685.5 1165.01  4806.4 1160.76  4881.8 1157.04  4906.4 1155.73
  4913.0 1156.17  4927.2 1152.53  4941.5 1150.15  4976.3 1145.75  4984.4 1143.39
  4991.0 1142.97  4991.6 1141.68  4992.1 1141.18  5000.9 1141.68  5026.1 1146.38
  5034.3 1147.62  5040.6 1147.47  5055.1 1150.81  5062.4 1151.38  5113.0 1150.40
  5162.9 1153.70  5176.4 1153.38  5272.1 1157.11  5397.2 1162.71  5492.4 1167.69
  5512.9 1169.01  5569.1 1172.35  5589.9 1172.79  5616.8 1175.09  5632.4 1176.15
#Mann=11,-1,0
  4671.8    0.12       0  4881.8    0.05       0  4976.3    0.12       0
  4991.6    0.07       0  5000.9    0.12       0  5162.9    0.05       0
  5272.1    0.12       0  5397.2    0.05       0  5492.4    0.12       0
  5512.9    0.05       0  5616.8    0.12       0
Bank Sta=4991.6,5000.9
Exp/Cntr=0.3,0.1

Type RM Length L Ch R = 1,2000,500,500,500
BEGIN DESCRIPTION:
HICKORY37 4.0
END DESCRIPTION:
XS GIS Cut Line= 3
      2768955.72     10216803.11      2769649.16     10216764.67
      2770055.72     10216703.11
#Sta/Elev= 30
  4305.5 1170.33  4355.5 1168.99  4398.2 1166.41  4573.7 1153.65  4726.1 1155.24
  4754.1 1154.53  4776.2 1154.91  4888.9 1149.90  4906.4 1149.38  4956.5 1145.63
  4991.1 1139.10  4991.6 1138.60  4999.9 1138.60  5000.4 1139.10  5026.8 1141.95
  5042.9 1141.95  5057.2 1144.82  5067.3 1145.49  5087.5 1143.30  5106.6 1147.35
  5169.0 1150.73  5219.0 1153.22  5229.1 1152.78  5239.2 1154.38  5244.2 1154.30
  5259.4 1156.17  5299.9 1158.47  5330.2 1161.29  5370.7 1162.53  5411.2 1165.00
#Mann=5,-1,0
  4305.5    0.12       0  4888.9    0.05       0  4991.1    0.07       0
  5000.4    0.05       0  5169.0    0.05       0
Bank Sta=4991.1,5000.4
Exp/Cntr=0.3,0.1

Type RM Length L Ch R = 1,1500,500,500,500
BEGIN DESCRIPTION:
HICKORY37 3.0
END DESCRIPTION:
XS GIS Cut Line= 3
      2769324.43     10217327.11      2769683.49     10217236.55
      2770105.69     10216903.11
#Sta/Elev= 30
  4629.7 1159.61  4662.8 1157.75  4666.8 1157.95  4682.6 1155.85  4766.1 1151.61
  4835.1 1148.39  4940.4 1143.60  4949.1 1142.71  4961.0 1139.64  4985.1 1137.35
  4985.6 1136.85  4995.3 1137.35  5004.6 1137.87  5011.4 1139.42  5032.2 1140.77
  5046.6 1140.00  5061.1 1142.81  5067.5 1142.19  5075.5 1144.32  5081.9 1143.57
  5090.0 1145.55  5096.3 1145.03  5110.8 1145.78  5125.2 1147.77  5174.9 1150.45
  5189.3 1152.14  5195.7 1151.35  5310.7 1155.49  5332.0 1157.04  5538.0 1163.59
#Mann=7,-1,0
  4629.7    0.05       0  4662.8    0.12       0  4766.1    0.05       0
  4835.1    0.12       0  4985.1    0.07       0  4995.3    0.12       0
  5310.7    0.05       0
Bank Sta=4985.1,4995.3
Exp/Cntr=0.3,0.1

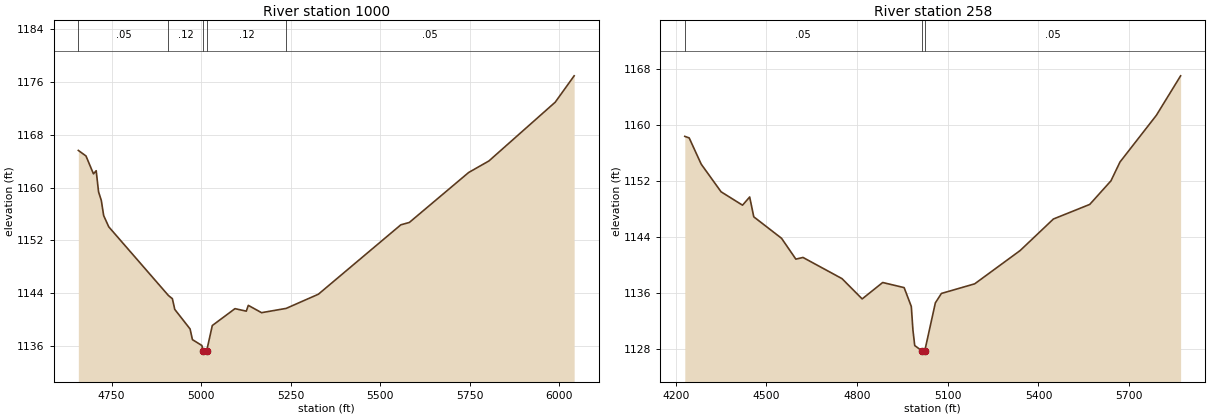
Type RM Length L Ch R = 1,1000,742,742,742
BEGIN DESCRIPTION:
HICKORY37 2.0
END DESCRIPTION:
XS GIS Cut Line= 3
      2769655.68     10217903.12      2769879.29     10217643.03
      2770205.67     10216653.15
#Sta/Elev= 30
  4657.0 1165.64  4678.4 1164.80  4699.3 1162.08  4706.9 1162.56  4713.5 1159.36
  4721.2 1158.05  4727.8 1155.75  4742.1 1154.04  4908.8 1143.62  4919.8 1143.14
  4926.4 1141.52  4969.2 1138.55  4975.8 1136.93  5002.2 1136.04  5005.3 1135.23
  5005.8 1134.73  5015.6 1135.23  5031.3 1139.07  5094.7 1141.63  5126.3 1141.25
  5131.9 1142.13  5168.9 1141.02  5237.7 1141.67  5327.7 1143.82  5558.0 1154.35
  5581.8 1154.71  5747.5 1162.29  5804.1 1164.04  5989.4 1172.96  6042.3 1176.96
#Mann=5,-1,0
  4657.0    0.05       0  4908.8    0.12       0  5005.3    0.07       0
  5015.6    0.12       0  5237.7    0.05       0
Bank Sta=5005.3,5015.6
Exp/Cntr=0.3,0.1

Type RM Length L Ch R = 1,258,0,0,0
BEGIN DESCRIPTION:
HICKORY37 1.0
END DESCRIPTION:
XS GIS Cut Line= 3
      2769805.68     10217953.11      2770514.25     10217652.00
      2770559.55     10216782.88
#Sta/Elev= 30
  4230.1 1158.34  4244.6 1158.12  4284.4 1154.38  4350.1 1150.44  4421.1 1148.53
  4444.7 1149.70  4458.3 1146.87  4550.2 1143.81  4597.5 1140.84  4621.1 1141.08
  4750.2 1138.06  4816.8 1135.17  4884.8 1137.51  4955.7 1136.78  4979.4 1134.09
  4984.8 1130.73  4990.7 1128.52  5013.7 1127.80  5014.2 1127.30  5024.1 1127.80
  5059.0 1134.61  5079.0 1135.95  5189.1 1137.32  5339.3 1142.06  5449.5 1146.56
  5569.7 1148.64  5639.8 1152.00  5669.8 1154.69  5790.0 1161.34  5870.3 1166.97
#Mann=3,-1,0
  4230.1    0.05       0  5013.7    0.05       0  5024.1    0.05       0
Bank Sta=5013.7,5024.1
Exp/Cntr=0.3,0.1

Chan Stop Cuts=-1