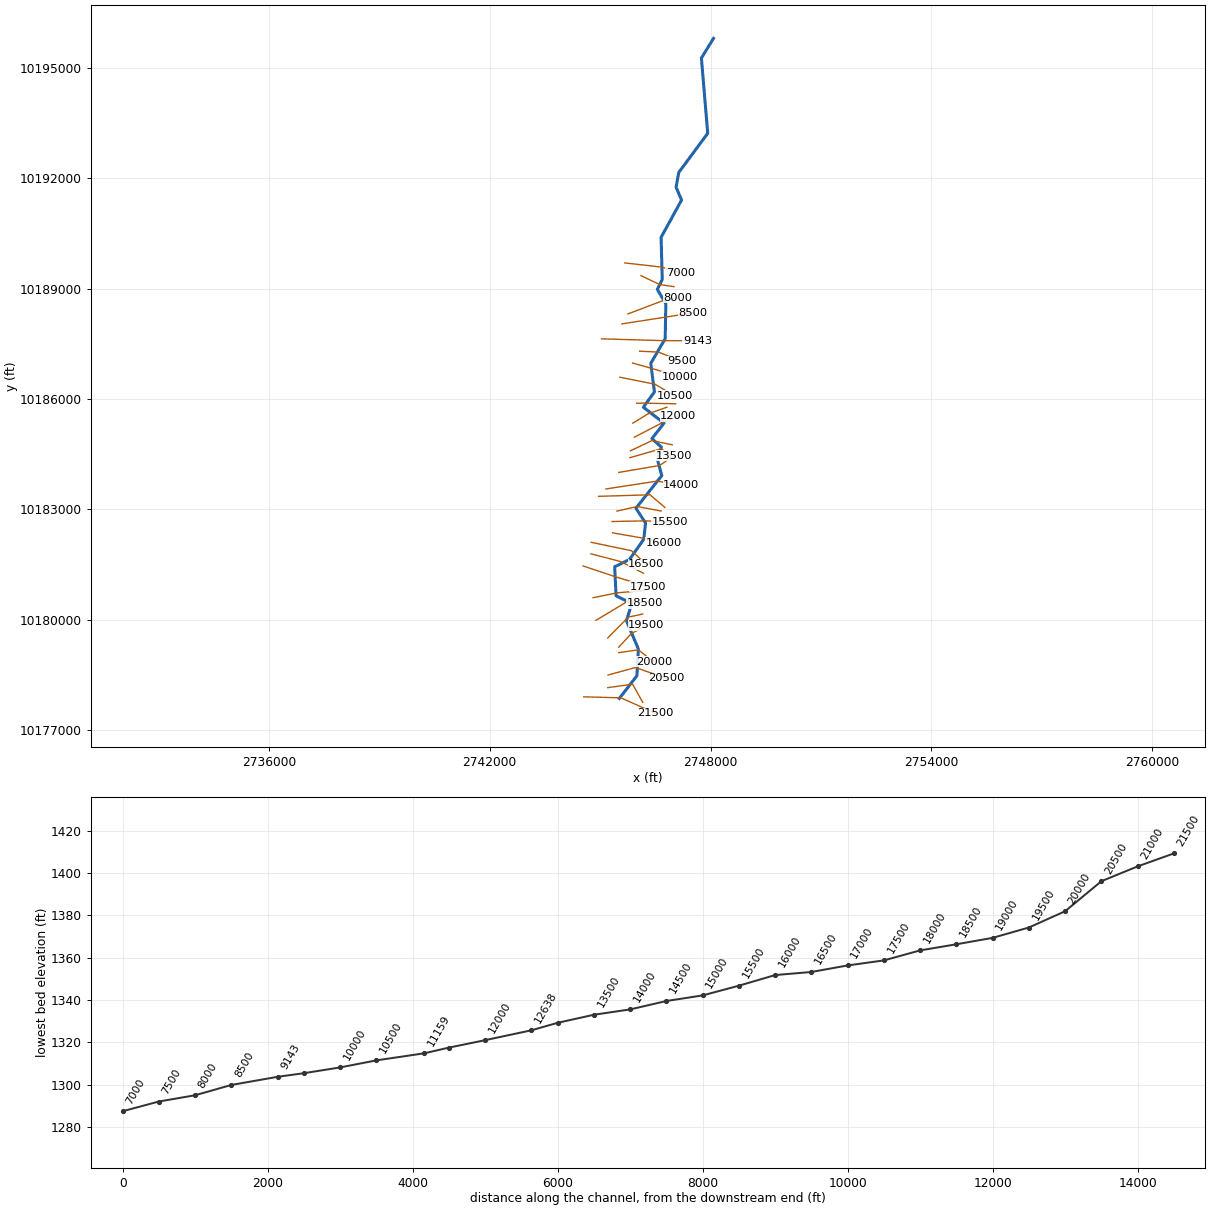
--- HOUSE MT BRANCH.prj (project) ---

Proj Title=HOUSE MT BRANCH Base Level Engineering
Current Plan=p01
Default Exp/Contr=0.3,0.1
English Units
Geom File=g01
Flow File=f01
Plan File=p01
BEGIN DESCRIPTION:
HOUSE MT BRANCH
END DESCRIPTION:

--- HOUSE MT BRANCH.p01 (plan) ---

Plan Title=Multiple Run
Short Identifier=Multiple
Geom File=g01
Flow File=f01
Subcritical Flow
K Sum by GR= 0
Std Step Tol= 0.01
Critical Tol= 0.01
Num of Std Step Trials= 20
Max Error Tol= 0.3
Flow Tol Ratio= 0.001
Split Flow NTrial= 30
Split Flow Tol= 0.02
Split Flow Ratio= 0.02
Log Output Level= 0
Friction Slope Method= 1
Unsteady Friction Slope Method= 2
Unsteady Bridges Friction Slope Method= 1
Parabolic Critical Depth
Global Vel Dist=  1 , 1 , 1
Global Log Level= 0
CheckData=True
Encroach Param= -1, 0, 0, 0
BEGIN DESCRIPTION:
Multiple Run
END DESCRIPTION:

--- HOUSE MT BRANCH.f01 (steady flow) ---

Flow Title=Multiple
Number of Profiles=7
Profile Names=10-year,25-year,50-year,1pct_min,100-year,1pct_plu,500-year
River Rch & RM= HOUSE MT BRANCH,Reach-1,21500
     379     604     757     585     991    1679    1342
River Rch & RM= HOUSE MT BRANCH,Reach-1,15500
     629    1041    1309     945    1747    3229    2363
River Rch & RM= HOUSE MT BRANCH,Reach-1,10000
     802    1345    1773    1287    2388    4431    3223
River Rch & RM= HOUSE MT BRANCH,Reach-1,8500
     992    1691    2247    1585    3055    5888    4132
River Rch & RM= HOUSE MT BRANCH,Reach-1,5000
    1153    1984    2776    1951    3814    7456    5183
River Rch & RM= HOUSE MT BRANCH,Reach-1,2500
    1275    2204    3184    2259    4396    8555    5968
River Rch & RM= HOUSE MT BRANCH,Reach-1,2000
    1364    2372    3344    2329    4619    9160    6264
Boundary for River Rch & Prof#=HOUSE MT BRANCH,Reach-1,1
Up Type=0
Dn Type=3
Dn Slope=0.005
Boundary for River Rch & Prof#=HOUSE MT BRANCH,Reach-1,2
Up Type=0
Dn Type=3
Dn Slope=0.005
Boundary for River Rch & Prof#=HOUSE MT BRANCH,Reach-1,3
Up Type=0
Dn Type=3
Dn Slope=0.005
Boundary for River Rch & Prof#=HOUSE MT BRANCH,Reach-1,4
Up Type=0
Dn Type=3
Dn Slope=0.005
Boundary for River Rch & Prof#=HOUSE MT BRANCH,Reach-1,5
Up Type=0
Dn Type=3
Dn Slope=0.005
Boundary for River Rch & Prof#=HOUSE MT BRANCH,Reach-1,6
Up Type=0
Dn Type=3
Dn Slope=0.005
Boundary for River Rch & Prof#=HOUSE MT BRANCH,Reach-1,7
Up Type=0
Dn Type=3
Dn Slope=0.005

--- HOUSE MT BRANCH.g01 (geometry) ---

Geom Title=Existing Conditions

River Reach=HOUSE MT BRANCH,Reach-1
Reach XY= 30
      2745518.75     10177857.00      2745997.25     10178475.00
      2746038.00     10179200.00      2745714.25     10179970.00
      2745856.50     10180440.00      2745431.75     10180649.00
      2745393.75     10181440.00      2745795.50     10181636.00
      2746186.25     10182189.00      2746231.75     10182631.00
      2745970.50     10183030.00      2746673.50     10183916.00
      2746554.75     10184356.00      2746661.00     10184694.00
      2746404.75     10184922.00      2746733.00     10185341.00
      2746173.50     10185775.00      2746473.50     10186191.00
      2746374.50     10186968.00      2746766.50     10187640.00
      2746783.00     10188587.00      2746551.75     10188978.00
      2746686.00     10189247.00      2746654.75     10190394.00
      2747211.00     10191406.00      2747062.00     10191756.00
      2747134.00     10192156.00      2747921.50     10193221.00
      2747749.75     10195266.00      2748078.50     10195803.00

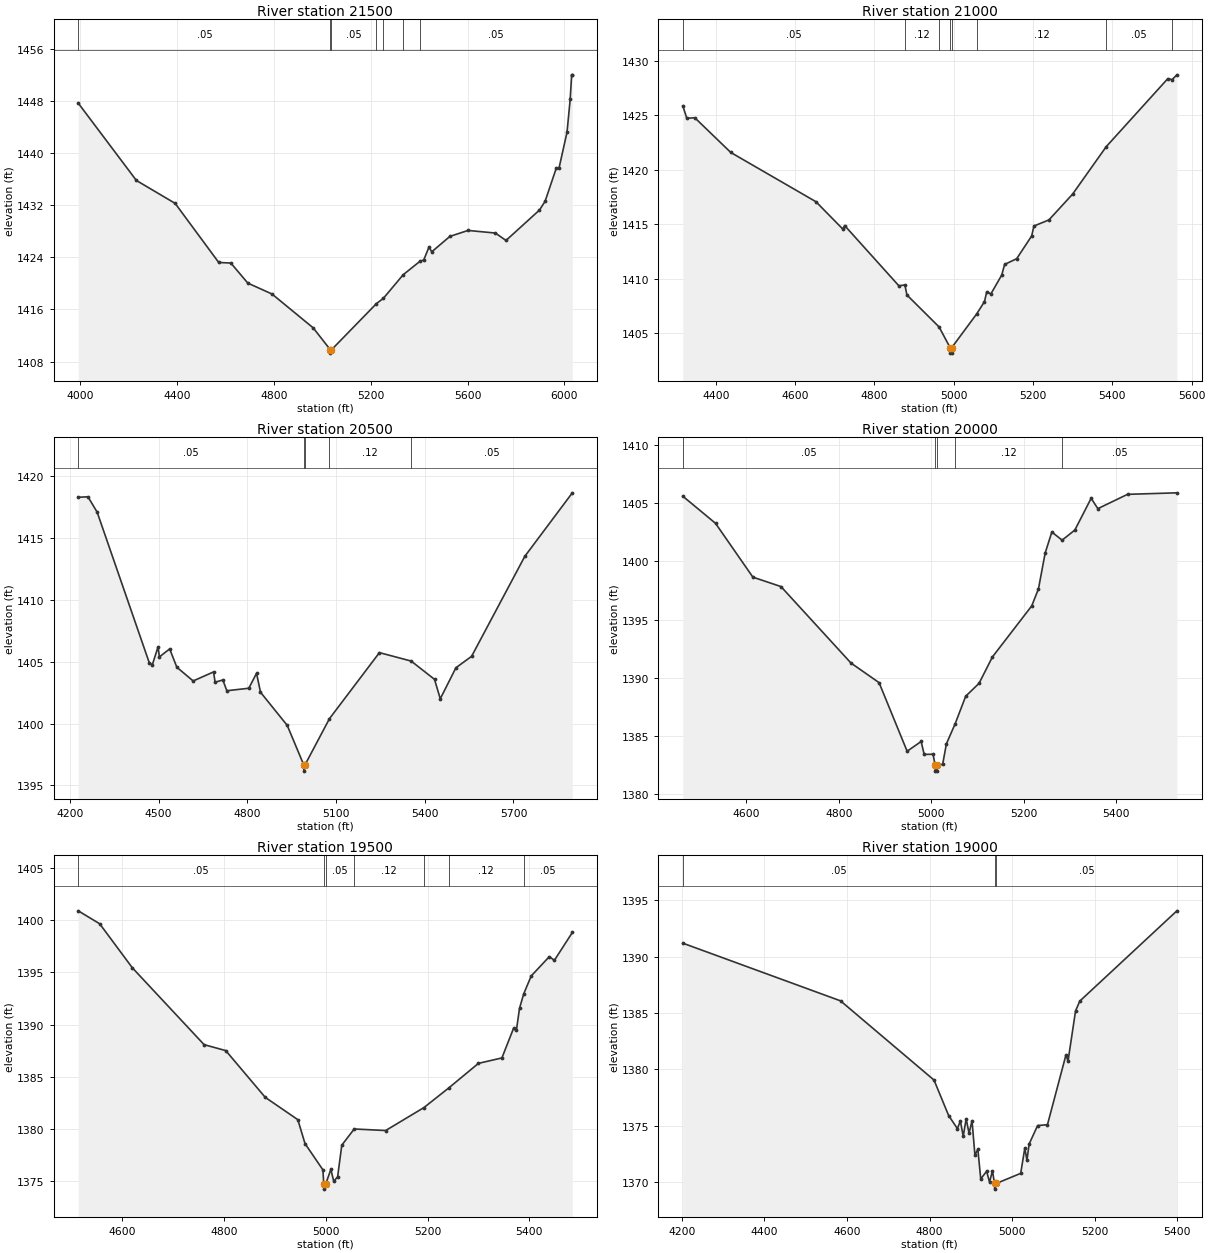
Type RM Length L Ch R = 1,21500,500,500,500
BEGIN DESCRIPTION:
HOUSE MT BRANCH 43.0
END DESCRIPTION:
XS GIS Cut Line= 3
      2744555.69     10177903.11      2745563.50     10177875.07
      2746505.72     10177453.10
#Sta/Elev= 30
  3991.8 1447.70  4231.9 1435.82  4392.0 1432.30  4572.0 1423.22  4622.0 1423.13
  4692.1 1420.05  4792.1 1418.37  4962.2 1413.17  5033.3 1409.79  5033.5 1409.29
  5037.3 1409.79  5223.4 1416.90  5252.0 1417.71  5333.7 1421.33  5402.7 1423.39
  5418.8 1423.61  5440.7 1425.62  5451.6 1424.85  5526.8 1427.23  5601.9 1428.14
  5714.6 1427.74  5758.4 1426.60  5896.6 1431.27  5919.8 1432.61  5966.2 1437.72
  5977.6 1437.75  6010.4 1443.23  6023.5 1448.26  6029.6 1452.05  6032.4 1452.05
#Mann=7,-1,0
  3991.8    0.05       0  5033.3    0.03       0  5037.3    0.05       0
  5223.4    0.12       0  5252.0    0.05       0  5333.7    0.12       0
  5402.7    0.05       0
Bank Sta=5033.3,5037.3
Exp/Cntr=0.3,0.1

Type RM Length L Ch R = 1,21000,500,500,500
BEGIN DESCRIPTION:
HOUSE MT BRANCH 42.0
END DESCRIPTION:
XS GIS Cut Line= 3
      2745205.72     10178153.12      2745882.68     10178245.26
      2746155.68     10177753.11
#Sta/Elev= 30
  4316.8 1425.87  4326.9 1424.72  4347.0 1424.77  4437.9 1421.58  4652.6 1417.06
  4720.0 1414.56  4725.0 1414.87  4861.7 1409.34  4876.9 1409.42  4881.9 1408.50
  4963.2 1405.56  4990.9 1403.66  4991.2 1403.16  4994.7 1403.16  4994.9 1403.66
  5057.9 1406.76  5077.6 1407.89  5083.3 1408.80  5093.6 1408.59  5121.1 1410.33
  5128.3 1411.30  5158.8 1411.83  5196.6 1413.92  5202.3 1414.83  5240.1 1415.39
  5299.6 1417.75  5384.7 1422.12  5539.9 1428.36  5550.8 1428.27  5562.8 1428.71
#Mann=8,-1,0
  4316.8    0.05       0  4876.9    0.12       0  4963.2    0.05       0
  4990.9    0.05       0  4994.9    0.05       0  5057.9    0.12       0
  5384.7    0.05       0  5550.8    0.12       0
Bank Sta=4990.9,4994.9
Exp/Cntr=0.3,0.1

Type RM Length L Ch R = 1,20500,500,500,500
BEGIN DESCRIPTION:
HOUSE MT BRANCH 41.0
END DESCRIPTION:
XS GIS Cut Line= 3
      2745214.06     10178496.06      2745958.50     10178699.72
      2746807.29     10178403.17
#Sta/Elev= 30
  4228.2 1418.29  4261.0 1418.33  4292.1 1417.09  4468.4 1404.91  4478.7 1404.74
  4497.8 1406.18  4502.9 1405.39  4537.4 1406.03  4561.6 1404.55  4616.8 1403.44
  4685.8 1404.17  4691.0 1403.34  4717.2 1403.52  4730.7 1402.65  4804.9 1402.85
  4831.2 1404.06  4844.5 1402.53  4934.9 1399.85  4990.9 1396.65  4991.2 1396.15
  4994.9 1396.65  5077.7 1400.39  5246.7 1405.73  5353.9 1405.05  5433.0 1403.57
  5452.5 1402.00  5505.5 1404.51  5558.4 1405.43  5738.5 1413.52  5899.1 1418.65
#Mann=5,-1,0
  4228.2    0.05       0  4990.9    0.05       0  4994.9    0.05       0
  5077.7    0.12       0  5353.9    0.05       0
Bank Sta=4990.9,4994.9
Exp/Cntr=0.3,0.1

Type RM Length L Ch R = 1,20000,500,500,500
BEGIN DESCRIPTION:
HOUSE MT BRANCH 40.0
END DESCRIPTION:
XS GIS Cut Line= 3
      2745505.72     10179103.12      2746037.57     10179180.13
      2746455.68     10178853.12
#Sta/Elev= 30
  4462.6 1405.61  4533.3 1403.28  4614.1 1398.65  4674.8 1397.84  4826.3 1391.26
  4886.9 1389.58  4947.6 1383.68  4977.9 1384.52  4984.4 1383.41  5003.6 1383.42
  5008.3 1382.47  5008.5 1381.97  5012.0 1381.97  5012.3 1382.47  5024.4 1382.56
  5032.5 1384.32  5051.5 1386.05  5074.2 1388.41  5103.1 1389.52  5132.0 1391.79
  5217.0 1396.18  5231.5 1397.64  5246.0 1400.72  5260.4 1402.53  5282.7 1401.83
  5310.2 1402.70  5345.4 1405.43  5359.9 1404.54  5424.1 1405.77  5530.8 1405.90
#Mann=5,-1,0
  4462.6    0.05       0  5008.3    0.05       0  5012.3    0.05       0
  5051.5    0.12       0  5282.7    0.05       0
Bank Sta=5008.3,5012.3
Exp/Cntr=0.3,0.1

Type RM Length L Ch R = 1,19500,500,500,500
BEGIN DESCRIPTION:
HOUSE MT BRANCH 39.0
END DESCRIPTION:
XS GIS Cut Line= 3
      2745505.69     10179253.11      2745835.59     10179611.21
      2746255.72     10179853.13
#Sta/Elev= 30
  4513.1 1400.87  4555.3 1399.63  4619.4 1395.43  4760.6 1388.08  4803.2 1387.51
  4880.9 1383.04  4944.9 1380.91  4959.1 1378.62  4994.3 1376.11  4995.9 1374.77
  4996.1 1374.27  4999.9 1374.77  5009.9 1376.16  5015.6 1375.01  5023.2 1375.45
  5031.4 1378.47  5055.8 1380.02  5117.7 1379.87  5193.1 1382.07  5242.0 1383.95
  5300.1 1386.29  5346.3 1386.81  5369.1 1389.63  5374.8 1389.45  5380.9 1391.55
  5389.3 1392.95  5404.0 1394.65  5439.5 1396.49  5449.5 1396.14  5484.8 1398.80
#Mann=7,-1,0
  4513.1    0.05       0  4995.9    0.03       0  4999.9    0.05       0
  5055.8    0.12       0  5193.1    0.05       0  5242.0    0.12       0
  5389.3    0.05       0
Bank Sta=4995.9,4999.9
Exp/Cntr=0.3,0.1

Type RM Length L Ch R = 1,19000,500,500,500
BEGIN DESCRIPTION:
HOUSE MT BRANCH 38.0
END DESCRIPTION:
XS GIS Cut Line= 3
      2745205.70     10179503.12      2745765.55     10180070.79
      2746155.66     10180153.11
#Sta/Elev= 30
  4202.7 1391.21  4584.5 1386.09  4810.8 1379.06  4846.2 1375.91  4867.4 1374.75
  4874.5 1375.43  4881.5 1374.08  4888.6 1375.61  4895.6 1374.34  4902.8 1375.45
  4909.8 1372.40  4916.9 1372.92  4923.9 1370.28  4938.1 1370.97  4945.2 1370.00
  4952.2 1371.01  4957.3 1369.88  4957.6 1369.38  4961.3 1369.88  5020.6 1370.78
  5030.6 1373.03  5035.7 1371.94  5041.0 1373.38  5061.5 1375.02  5085.4 1375.10
  5130.1 1381.28  5135.2 1380.75  5153.4 1385.20  5163.7 1386.07  5398.7 1394.08
#Mann=3,-1,0
  4202.7    0.05       0  4957.3    0.05       0  4961.3    0.05       0
Bank Sta=4957.3,4961.3
Exp/Cntr=0.3,0.1

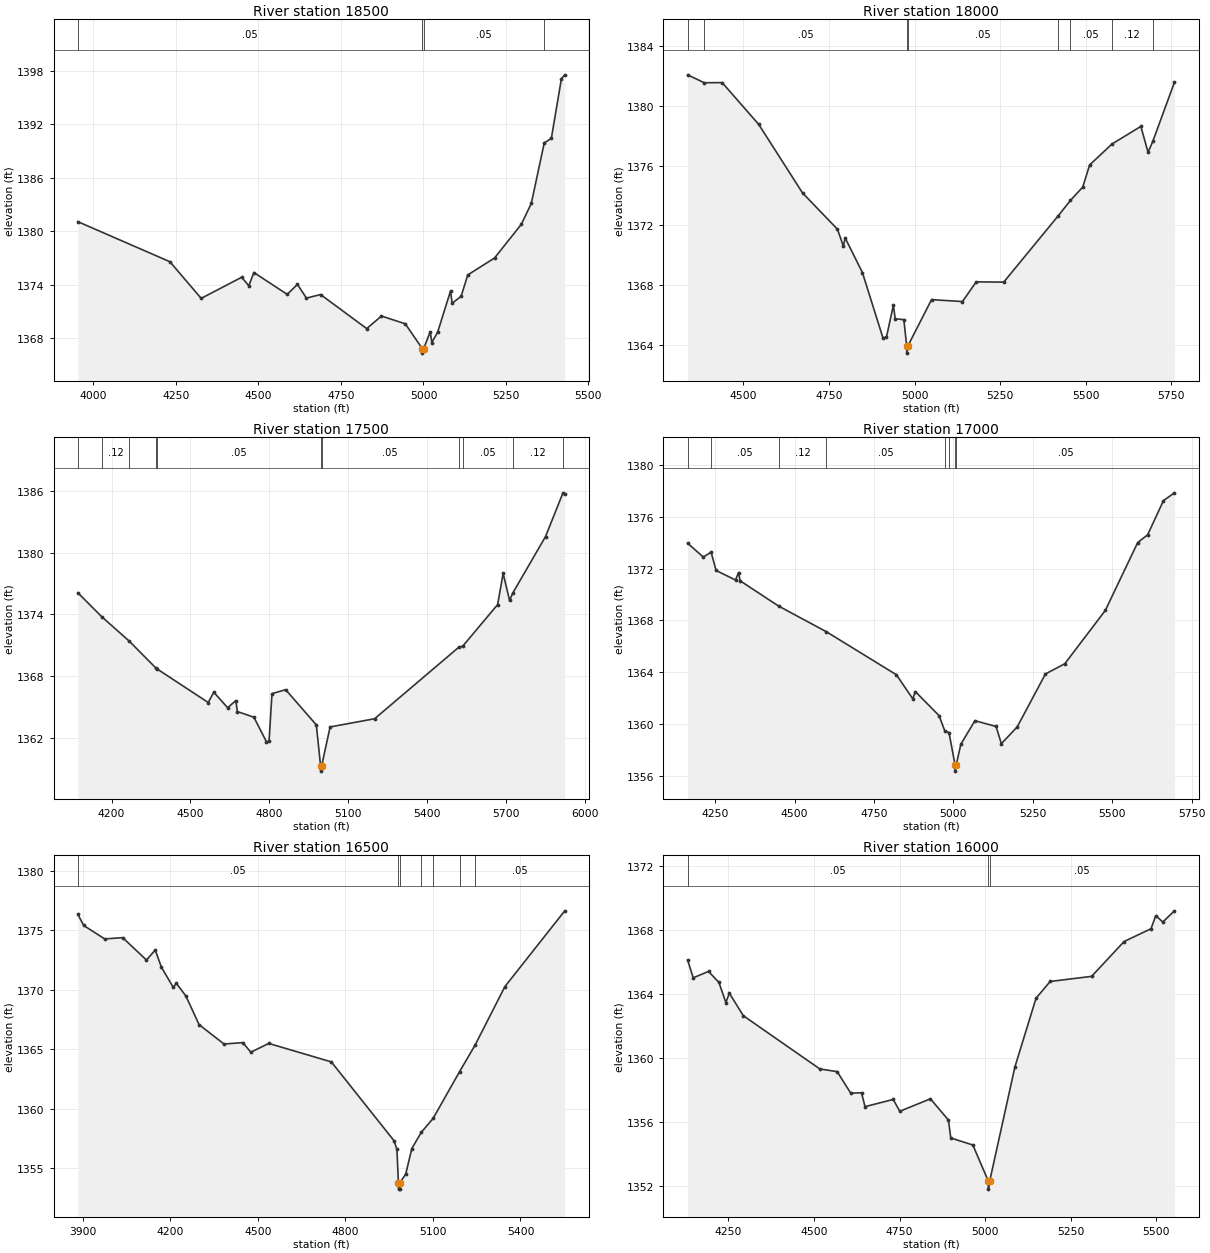
Type RM Length L Ch R = 1,18500,500,500,500
BEGIN DESCRIPTION:
HOUSE MT BRANCH 37.0
END DESCRIPTION:
XS GIS Cut Line= 3
      2744885.44     10179982.12      2745782.99     10180521.78
      2746205.65     10180453.12
#Sta/Elev= 30
  3952.7 1381.09  4231.6 1376.60  4326.4 1372.49  4449.2 1374.86  4470.6 1373.90
  4486.1 1375.39  4587.1 1372.94  4618.1 1374.06  4645.4 1372.52  4688.2 1372.92
  4828.1 1369.10  4872.7 1370.51  4944.8 1369.64  4996.7 1366.85  4996.9 1366.35
  5000.7 1366.85  5020.4 1368.74  5025.5 1367.54  5043.3 1368.73  5082.0 1373.31
  5087.0 1371.94  5114.2 1372.73  5134.4 1375.12  5215.5 1377.02  5296.5 1380.79
  5326.9 1383.14  5366.0 1389.91  5387.7 1390.45  5418.1 1397.12  5428.2 1397.56
#Mann=4,-1,0
  3952.7    0.05       0  4996.7    0.05       0  5000.7    0.05       0
  5366.0    0.12       0
Bank Sta=4996.7,5000.7
Exp/Cntr=0.3,0.1

Type RM Length L Ch R = 1,18000,500,500,500
BEGIN DESCRIPTION:
HOUSE MT BRANCH 36.0
END DESCRIPTION:
XS GIS Cut Line= 3
      2744806.77     10180596.51      2745456.52     10180729.43
      2746212.45     10180796.40
#Sta/Elev= 30
  4336.8 1382.08  4385.5 1381.55  4437.8 1381.56  4544.7 1378.76  4672.5 1374.18
  4774.6 1371.75  4791.9 1370.61  4797.0 1371.17  4847.5 1368.85  4907.3 1364.49
  4917.5 1364.51  4937.9 1366.66  4943.3 1365.76  4968.5 1365.70  4976.7 1363.96
  4977.0 1363.46  4980.7 1363.96  5049.4 1367.04  5139.7 1366.91  5179.9 1368.23
  5260.2 1368.21  5419.2 1372.64  5455.2 1373.68  5491.1 1374.57  5511.2 1376.05
  5576.4 1377.45  5660.8 1378.63  5681.8 1376.90  5695.6 1377.62  5758.9 1381.58
#Mann=8,-1,0
  4336.8    0.12       0  4385.5    0.05       0  4976.7    0.03       0
  4980.7    0.05       0  5419.2    0.12       0  5455.2    0.05       0
  5576.4    0.12       0  5695.6    0.05       0
Bank Sta=4976.7,4980.7
Exp/Cntr=0.3,0.1

Type RM Length L Ch R = 1,17500,500,500,500
BEGIN DESCRIPTION:
HOUSE MT BRANCH 35.0
END DESCRIPTION:
XS GIS Cut Line= 3
      2744535.33     10181460.99      2745415.35     10181165.81
      2746299.99     10180896.59
#Sta/Elev= 30
  4071.8 1376.09  4162.2 1373.77  4267.9 1371.37  4369.3 1368.75  4373.6 1368.67
  4567.9 1365.41  4589.1 1366.41  4641.7 1364.90  4673.2 1365.60  4678.5 1364.53
  4741.6 1363.98  4789.4 1361.59  4799.4 1361.63  4810.5 1366.27  4862.5 1366.66
  4979.3 1363.23  4995.5 1359.23  4995.8 1358.73  4999.5 1359.23  5031.7 1363.03
  5201.2 1363.83  5520.6 1370.77  5537.0 1370.91  5669.3 1374.94  5690.2 1377.97
  5714.9 1375.34  5726.8 1376.06  5851.5 1381.56  5918.1 1385.82  5924.7 1385.68
#Mann=11,-1,0
  4071.8    0.05       0  4162.2    0.12       0  4267.9    0.05       0
  4369.3    0.12       0  4373.6    0.05       0  4995.5    0.05       0
  4999.5    0.05       0  5520.6    0.12       0  5537.0    0.05       0
  5726.8    0.12       0  5918.1    0.05       0
Bank Sta=4995.5,4999.5
Exp/Cntr=0.3,0.1

Type RM Length L Ch R = 1,17000,500,500,500
BEGIN DESCRIPTION:
HOUSE MT BRANCH 34.0
END DESCRIPTION:
XS GIS Cut Line= 3
      2744749.65     10181789.64      2745559.49     10181578.56
      2746178.57     10181260.94
#Sta/Elev= 30
  4163.1 1373.97  4212.3 1372.90  4237.2 1373.27  4252.8 1371.86  4314.0 1371.12
  4323.5 1371.70  4328.6 1371.06  4450.1 1369.10  4599.6 1367.13  4820.4 1363.80
  4872.1 1361.94  4880.0 1362.50  4954.7 1360.64  4972.7 1359.47  4986.1 1359.33
  5005.0 1356.85  5005.2 1356.35  5009.0 1356.85  5023.4 1358.43  5067.7 1360.25
  5134.3 1359.80  5150.9 1358.47  5200.9 1359.77  5289.7 1363.86  5350.6 1364.65
  5478.2 1368.77  5580.2 1374.02  5611.3 1374.61  5661.3 1377.26  5695.8 1377.86
#Mann=8,-1,0
  4163.1    0.12       0  4237.2    0.05       0  4450.1    0.12       0
  4599.6    0.05       0  4972.7    0.12       0  4986.1    0.05       0
  5005.0    0.05       0  5009.0    0.05       0
Bank Sta=5005,5009
Exp/Cntr=0.3,0.1

Type RM Length L Ch R = 1,16500,500,500,500
BEGIN DESCRIPTION:
HOUSE MT BRANCH 33.0
END DESCRIPTION:
XS GIS Cut Line= 3
      2744755.65     10182103.12      2745848.35     10181875.25
      2746255.66     10181503.13
#Sta/Elev= 30
  3883.8 1376.32  3903.7 1375.39  3975.8 1374.26  4037.1 1374.37  4118.8 1372.49
  4148.8 1373.33  4169.9 1371.89  4210.7 1370.19  4220.9 1370.54  4253.9 1369.47
  4298.9 1367.07  4384.4 1365.44  4449.0 1365.56  4476.3 1364.75  4537.6 1365.49
  4752.1 1363.94  4966.6 1357.33  4976.8 1356.60  4982.0 1353.76  4982.2 1353.26
  4985.7 1353.26  4986.0 1353.76  5006.9 1354.52  5027.8 1356.67  5060.7 1358.04
  5100.6 1359.19  5191.4 1363.12  5245.0 1365.37  5346.7 1370.26  5551.7 1376.62
#Mann=7,-1,0
  3883.8    0.05       0  4982.0    0.05       0  4986.0    0.05       0
  5060.7    0.12       0  5100.6    0.05       0  5191.4    0.12       0
  5245.0    0.05       0
Bank Sta=4982,4986
Exp/Cntr=0.3,0.1

Type RM Length L Ch R = 1,16000,500,500,500
BEGIN DESCRIPTION:
HOUSE MT BRANCH 32.0
END DESCRIPTION:
XS GIS Cut Line= 3
      2745335.52     10182361.19      2746191.25     10182211.07
      2746728.70     10182082.55
#Sta/Elev= 30
  4131.2 1366.13  4147.8 1365.02  4192.3 1365.42  4222.7 1364.73  4243.0 1363.47
  4253.2 1364.06  4293.8 1362.65  4517.2 1359.32  4567.9 1359.15  4607.7 1357.80
  4639.0 1357.83  4649.2 1356.96  4731.6 1357.41  4750.7 1356.67  4840.2 1357.45
  4892.8 1356.12  4899.6 1355.00  4964.1 1354.56  5009.2 1352.30  5009.5 1351.80
  5013.2 1352.30  5086.8 1359.44  5148.5 1363.74  5189.7 1364.79  5310.8 1365.11
  5405.6 1367.29  5484.2 1368.09  5498.1 1368.91  5518.7 1368.51  5552.6 1369.21
#Mann=3,-1,0
  4131.2    0.05       0  5009.2    0.05       0  5013.2    0.05       0
Bank Sta=5009.2,5013.2
Exp/Cntr=0.3,0.1

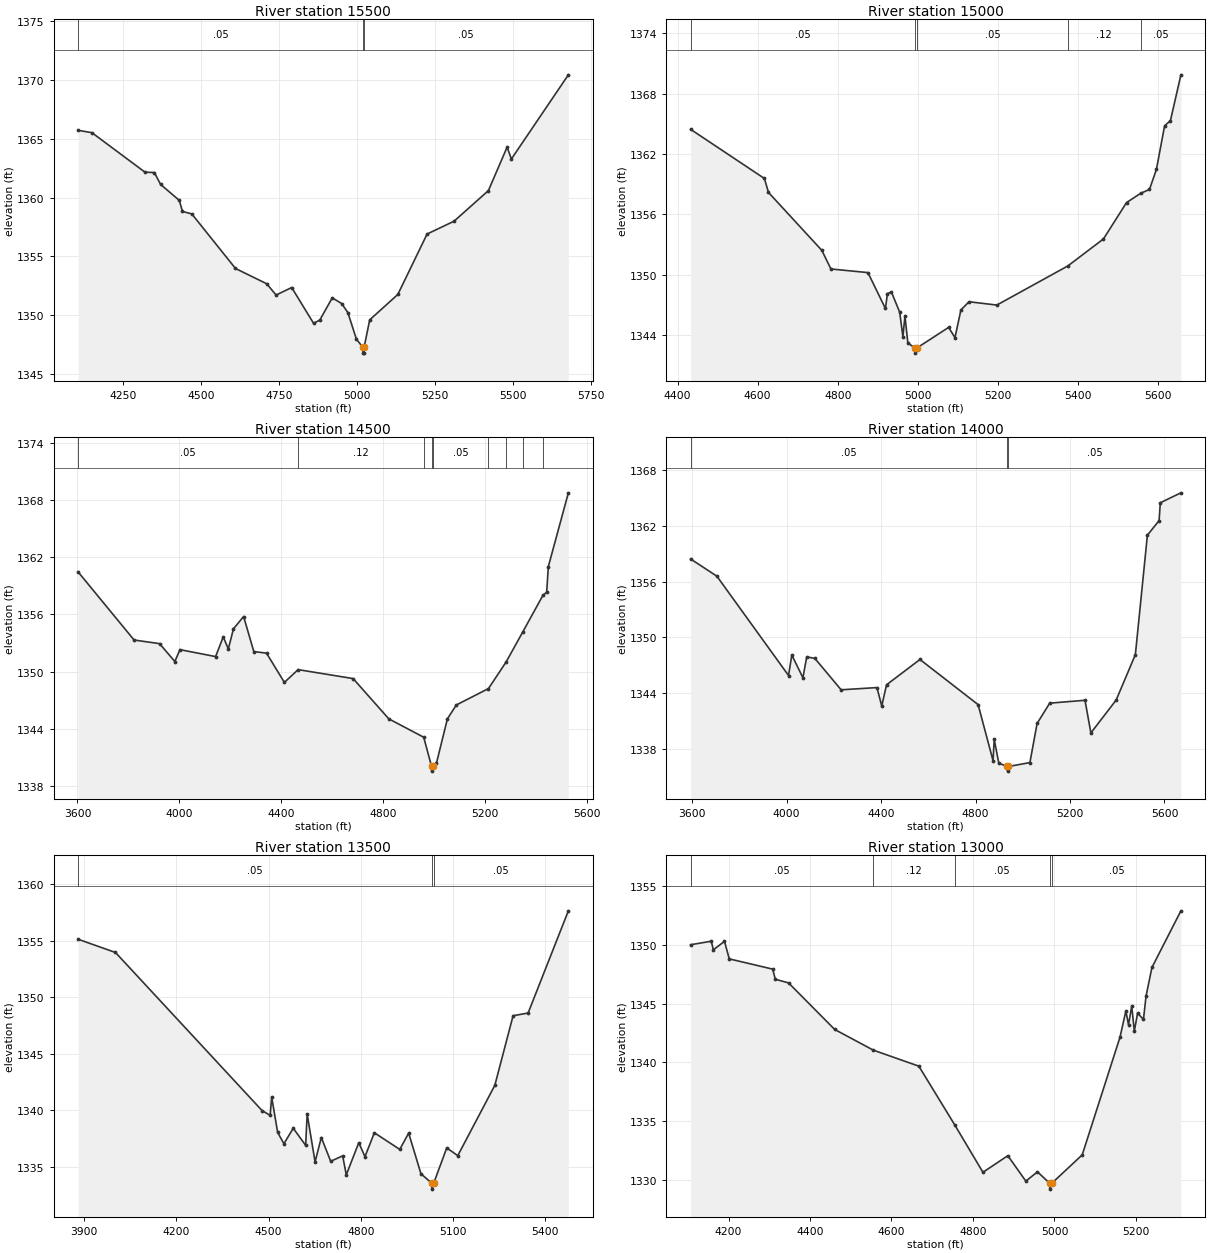
Type RM Length L Ch R = 1,15500,500,500,500
BEGIN DESCRIPTION:
HOUSE MT BRANCH 31.0
END DESCRIPTION:
XS GIS Cut Line= 3
      2745321.26     10182668.40      2746215.68     10182686.36
      2746891.81     10182661.30
#Sta/Elev= 30
  4105.4 1365.73  4149.8 1365.53  4319.9 1362.17  4349.9 1362.14  4369.9 1361.13
  4429.9 1359.77  4439.9 1358.83  4469.9 1358.62  4609.9 1353.98  4709.9 1352.68
  4740.0 1351.72  4790.0 1352.36  4860.0 1349.32  4880.0 1349.59  4920.0 1351.48
  4950.0 1351.00  4970.0 1350.23  4997.5 1347.96  5018.0 1347.28  5018.3 1346.78
  5021.8 1346.78  5022.1 1347.28  5040.0 1349.61  5130.1 1351.77  5223.9 1356.91
  5310.2 1358.00  5420.3 1360.60  5480.3 1364.30  5494.0 1363.29  5676.6 1370.45
#Mann=3,-1,0
  4105.4    0.05       0  5018.0    0.05       0  5022.1    0.05       0
Bank Sta=5018,5022.1
Exp/Cntr=0.3,0.1

Type RM Length L Ch R = 1,15000,500,500,500
BEGIN DESCRIPTION:
HOUSE MT BRANCH 30.0
END DESCRIPTION:
XS GIS Cut Line= 3
      2745455.66     10182953.11      2746009.90     10183075.50
      2746655.71     10182953.11
#Sta/Elev= 30
  4432.4 1364.45  4616.8 1359.56  4627.0 1358.17  4760.1 1352.42  4783.0 1350.56
  4875.4 1350.20  4919.1 1346.63  4924.2 1348.11  4934.2 1348.26  4954.7 1346.27
  4962.8 1343.83  4967.9 1345.89  4975.2 1343.20  4993.2 1342.69  4993.5 1342.19
  4997.3 1342.69  5077.1 1344.75  5092.9 1343.73  5107.7 1346.48  5128.0 1347.30
  5197.5 1346.97  5375.2 1350.87  5463.9 1353.55  5521.4 1357.16  5556.5 1358.08
  5578.8 1358.47  5596.2 1360.47  5616.6 1364.80  5631.1 1365.31  5657.3 1369.87
#Mann=5,-1,0
  4432.4    0.05       0  4993.2    0.05       0  4997.3    0.05       0
  5375.2    0.12       0  5556.5    0.05       0
Bank Sta=4993.2,4997.3
Exp/Cntr=0.3,0.1

Type RM Length L Ch R = 1,14500,500,500,500
BEGIN DESCRIPTION:
HOUSE MT BRANCH 29.0
END DESCRIPTION:
XS GIS Cut Line= 3
      2744955.66     10183353.11      2746352.75     10183394.61
      2746755.70     10183053.10
#Sta/Elev= 30
  3602.3 1360.47  3822.4 1353.31  3922.5 1352.93  3982.5 1351.05  4002.5 1352.30
  4142.6 1351.57  4172.6 1353.64  4192.6 1352.37  4212.6 1354.48  4252.6 1355.78
  4292.6 1352.10  4342.6 1351.93  4412.7 1348.86  4466.8 1350.20  4682.8 1349.26
  4822.9 1345.03  4960.0 1343.10  4990.8 1340.04  4991.1 1339.54  4995.0 1340.04
  5010.2 1340.39  5053.1 1345.03  5088.2 1346.49  5214.3 1348.21  5283.4 1350.99
  5348.7 1354.14  5428.0 1357.99  5443.0 1358.34  5449.6 1361.03  5528.2 1368.77
#Mann=9,-1,0
  3602.3    0.05       0  4466.8    0.12       0  4960.0    0.05       0
  4990.8    0.05       0  4995.0    0.05       0  5214.3    0.12       0
  5283.4    0.05       0  5348.7    0.12       0  5428.0    0.05       0
Bank Sta=4990.8,4995
Exp/Cntr=0.3,0.1

Type RM Length L Ch R = 1,14000,500,500,500
BEGIN DESCRIPTION:
HOUSE MT BRANCH 28.0
END DESCRIPTION:
XS GIS Cut Line= 3
      2745155.67     10183553.11      2746545.79     10183767.14
      2747205.71     10183653.11
#Sta/Elev= 30
  3593.5 1358.45  3704.8 1356.59  4008.3 1345.88  4022.1 1348.09  4069.1 1345.64
  4085.3 1347.89  4119.6 1347.73  4230.9 1344.34  4382.7 1344.58  4402.9 1342.59
  4423.2 1344.88  4564.8 1347.61  4811.0 1342.74  4874.2 1336.70  4879.2 1338.99
  4898.7 1336.42  4935.3 1336.07  4935.6 1335.57  4939.5 1336.07  5030.3 1336.49
  5060.8 1340.71  5114.2 1342.90  5263.7 1343.21  5288.5 1339.69  5395.7 1343.24
  5476.9 1348.13  5527.8 1361.01  5577.4 1362.59  5582.5 1364.51  5669.7 1365.58
#Mann=3,-1,0
  3593.5    0.05       0  4935.3    0.03       0  4939.5    0.05       0
Bank Sta=4935.3,4939.5
Exp/Cntr=0.3,0.1

Type RM Length L Ch R = 1,13500,500,500,500
BEGIN DESCRIPTION:
HOUSE MT BRANCH 27.0
END DESCRIPTION:
XS GIS Cut Line= 3
      2745505.68     10184003.11      2746609.50     10184191.01
      2747005.65     10184453.09
#Sta/Elev= 30
  3880.3 1355.13  4002.0 1353.96  4478.8 1339.99  4505.1 1339.57  4510.1 1341.18
  4529.5 1338.06  4549.8 1337.06  4580.2 1338.43  4620.5 1336.92  4625.5 1339.68
  4651.2 1335.46  4671.5 1337.61  4702.0 1335.51  4740.9 1335.99  4752.7 1334.31
  4793.3 1337.15  4813.5 1335.92  4844.0 1338.03  4926.7 1336.56  4955.6 1338.00
  4995.5 1334.41  5031.7 1333.55  5032.1 1333.05  5036.7 1333.55  5079.4 1336.69
  5115.3 1336.01  5235.8 1342.22  5295.2 1348.37  5344.1 1348.61  5475.0 1357.64
#Mann=3,-1,0
  3880.3    0.05       0  5031.7    0.03       0  5036.7    0.05       0
Bank Sta=5031.7,5036.7
Exp/Cntr=0.3,0.1

Type RM Length L Ch R = 1,13000,362,362,362
BEGIN DESCRIPTION:
HOUSE MT BRANCH 26.0
END DESCRIPTION:
XS GIS Cut Line= 3
      2745805.72     10184403.12      2746664.45     10184648.48
      2746905.67     10184453.12
#Sta/Elev= 30
  4106.9 1349.99  4157.6 1350.29  4162.8 1349.56  4190.1 1350.28  4201.8 1348.79
  4308.4 1347.92  4314.9 1347.06  4347.4 1346.75  4460.5 1342.80  4555.4 1341.04
  4667.2 1339.68  4755.5 1334.68  4824.5 1330.67  4885.6 1332.08  4929.8 1329.92
  4958.4 1330.71  4988.2 1329.74  4988.6 1329.24  4993.6 1329.74  5068.2 1332.15
  5161.0 1342.15  5175.3 1344.37  5181.8 1343.20  5189.7 1344.78  5196.1 1342.66
  5204.1 1344.18  5218.5 1343.65  5224.9 1345.64  5239.3 1348.06  5310.4 1352.87
#Mann=5,-1,0
  4106.9    0.05       0  4555.4    0.12       0  4755.5    0.05       0
  4988.2    0.05       0  4993.6    0.05       0
Bank Sta=4988.2,4993.6
Exp/Cntr=0.3,0.1

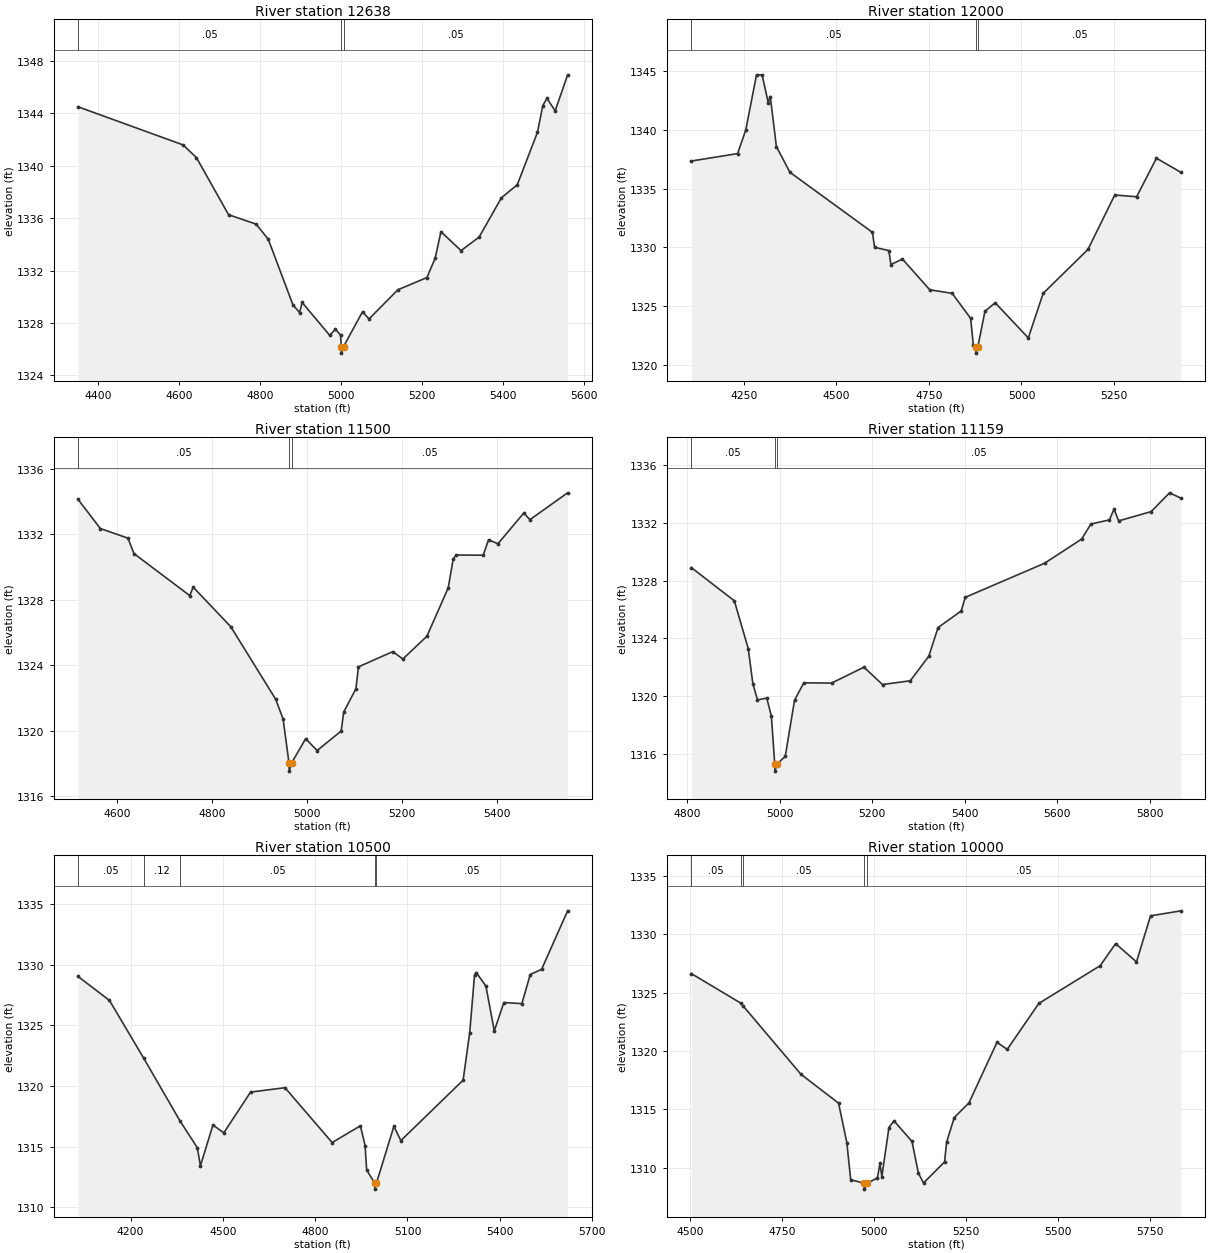
Type RM Length L Ch R = 1,12638,638,638,638
BEGIN DESCRIPTION:
HOUSE MT BRANCH 25.0
END DESCRIPTION:
XS GIS Cut Line= 3
      2745821.35     10184590.26      2746408.00     10184869.00
      2746955.67     10184753.11
#Sta/Elev= 30
  4350.5 1344.51  4609.9 1341.60  4643.0 1340.63  4722.3 1336.27  4790.4 1335.55
  4820.3 1334.40  4881.3 1329.39  4897.8 1328.79  4904.0 1329.57  4972.2 1327.06
  4986.4 1327.53  4999.0 1327.07  5000.8 1326.20  5001.2 1325.70  5006.3 1326.20
  5053.2 1328.86  5069.2 1328.31  5140.7 1330.54  5212.3 1331.47  5232.7 1332.95
  5246.9 1334.97  5296.6 1333.53  5341.2 1334.56  5396.3 1337.56  5435.5 1338.56
  5485.3 1342.56  5498.5 1344.60  5508.7 1345.15  5529.1 1344.20  5559.8 1346.95
#Mann=3,-1,0
  4350.5    0.05       0  5000.8    0.03       0  5006.3    0.05       0
Bank Sta=5000.8,5006.3
Exp/Cntr=0.3,0.1

Type RM Length L Ch R = 1,12000,500,500,500
BEGIN DESCRIPTION:
HOUSE MT BRANCH 24.0
END DESCRIPTION:
XS GIS Cut Line= 3
      2745929.30     10184960.75      2746721.25     10185372.09
      2747121.14     10185533.12
#Sta/Elev= 30
  4107.6 1337.33  4232.6 1337.96  4254.7 1339.95  4283.8 1344.64  4298.9 1344.64
  4315.4 1342.28  4321.0 1342.80  4337.5 1338.56  4374.0 1336.38  4597.3 1331.28
  4602.9 1330.01  4641.5 1329.74  4647.1 1328.55  4678.2 1329.02  4752.1 1326.41
  4812.8 1326.11  4862.7 1323.98  4869.8 1321.73  4876.4 1321.54  4876.9 1321.04
  4881.9 1321.54  4901.3 1324.59  4929.0 1325.31  5018.5 1322.33  5058.7 1326.11
  5179.7 1329.83  5252.2 1334.45  5311.3 1334.30  5365.0 1337.57  5431.1 1336.37
#Mann=3,-1,0
  4107.6    0.05       0  4876.4    0.05       0  4881.9    0.05       0
Bank Sta=4876.4,4881.9
Exp/Cntr=0.3,0.1

Type RM Length L Ch R = 1,11500,341,341,341
BEGIN DESCRIPTION:
HOUSE MT BRANCH 23.0
END DESCRIPTION:
XS GIS Cut Line= 3
      2745885.58     10185340.39      2746295.60     10185593.22
      2746812.58     10185775.58
#Sta/Elev= 30
  4518.3 1334.12  4565.3 1332.34  4623.3 1331.75  4635.9 1330.81  4753.4 1328.24
  4760.5 1328.76  4839.7 1326.34  4934.3 1321.90  4949.7 1320.70  4962.1 1318.02
  4962.6 1317.52  4967.6 1318.02  4997.1 1319.50  5021.3 1318.78  5071.9 1319.97
  5077.2 1321.13  5102.9 1322.55  5108.2 1323.89  5180.4 1324.82  5201.6 1324.37
  5252.2 1325.76  5297.0 1328.71  5307.6 1330.49  5314.1 1330.72  5370.7 1330.71
  5381.8 1331.65  5401.6 1331.41  5456.1 1333.29  5468.8 1332.88  5548.2 1334.52
#Mann=3,-1,0
  4518.3    0.05       0  4962.1    0.05       0  4967.6    0.05       0
Bank Sta=4962.1,4967.6
Exp/Cntr=0.3,0.1

Type RM Length L Ch R = 1,11159,659,659,659
BEGIN DESCRIPTION:
HOUSE MT BRANCH 22.0
END DESCRIPTION:
XS GIS Cut Line= 3
      2745992.82     10185883.39      2746183.50     10185886.00
      2747050.14     10185869.10
#Sta/Elev= 30
  4809.3 1328.90  4902.2 1326.60  4932.2 1323.30  4942.2 1320.87  4952.2 1319.75
  4972.2 1319.87  4982.2 1318.63  4989.4 1315.32  4989.8 1314.82  4994.9 1315.32
  5012.2 1315.85  5032.2 1319.72  5052.2 1320.93  5112.2 1320.91  5182.2 1322.01
  5222.2 1320.81  5282.2 1321.07  5322.2 1322.77  5342.2 1324.75  5392.3 1325.90
  5400.9 1326.84  5572.3 1329.20  5652.3 1330.87  5672.3 1331.91  5712.3 1332.20
  5722.3 1332.94  5732.3 1332.13  5802.3 1332.77  5842.3 1334.07  5866.8 1333.70
#Mann=3,-1,0
  4809.3    0.05       0  4989.4    0.05       0  4994.9    0.05       0
Bank Sta=4989.4,4994.9
Exp/Cntr=0.3,0.1

Type RM Length L Ch R = 1,10500,500,500,500
BEGIN DESCRIPTION:
HOUSE MT BRANCH 21.0
END DESCRIPTION:
XS GIS Cut Line= 3
      2745535.52     10186590.69      2746487.65     10186400.73
      2747021.16     10186083.69
#Sta/Elev= 30
  4029.1 1329.02  4131.2 1327.05  4242.2 1322.30  4360.9 1317.10  4416.8 1314.91
  4427.0 1313.41  4467.7 1316.78  4502.9 1316.13  4590.1 1319.49  4701.9 1319.85
  4855.1 1315.33  4947.0 1316.71  4962.3 1315.08  4967.4 1313.06  4993.6 1311.99
  4994.1 1311.49  4999.2 1311.99  5055.9 1316.67  5078.4 1315.49  5280.9 1320.47
  5302.4 1324.40  5318.0 1329.13  5323.8 1329.34  5355.0 1328.23  5382.2 1324.53
  5413.4 1326.87  5471.9 1326.78  5499.1 1329.18  5536.1 1329.61  5620.6 1334.43
#Mann=5,-1,0
  4029.1    0.05       0  4242.2    0.12       0  4360.9    0.05       0
  4993.6    0.05       0  4999.2    0.05       0
Bank Sta=4993.6,4999.2
Exp/Cntr=0.3,0.1

Type RM Length L Ch R = 1,10000,500,500,500
BEGIN DESCRIPTION:
HOUSE MT BRANCH 20.0
END DESCRIPTION:
XS GIS Cut Line= 3
      2745878.50     10186976.48      2746356.78     10186843.22
      2747155.68     10186603.11
#Sta/Elev= 30
  4503.5 1326.64  4637.2 1324.12  4643.6 1323.89  4801.6 1318.00  4903.7 1315.53
  4926.2 1312.14  4936.6 1308.97  4973.4 1308.66  4973.9 1308.16  4981.3 1308.66
  5009.3 1309.12  5016.1 1310.36  5021.3 1309.24  5040.6 1313.44  5054.4 1314.01
  5103.3 1312.25  5120.5 1309.54  5134.6 1308.69  5191.7 1310.49  5197.3 1312.18
  5218.1 1314.30  5257.8 1315.54  5334.3 1320.75  5362.1 1320.14  5447.9 1324.08
  5614.9 1327.32  5656.7 1329.21  5713.4 1327.64  5751.6 1331.59  5834.2 1332.02
#Mann=5,-1,0
  4503.5    0.05       0  4637.2    0.12       0  4643.6    0.05       0
  4973.4    0.03       0  4981.3    0.05       0
Bank Sta=4973.4,4981.3
Exp/Cntr=0.3,0.1

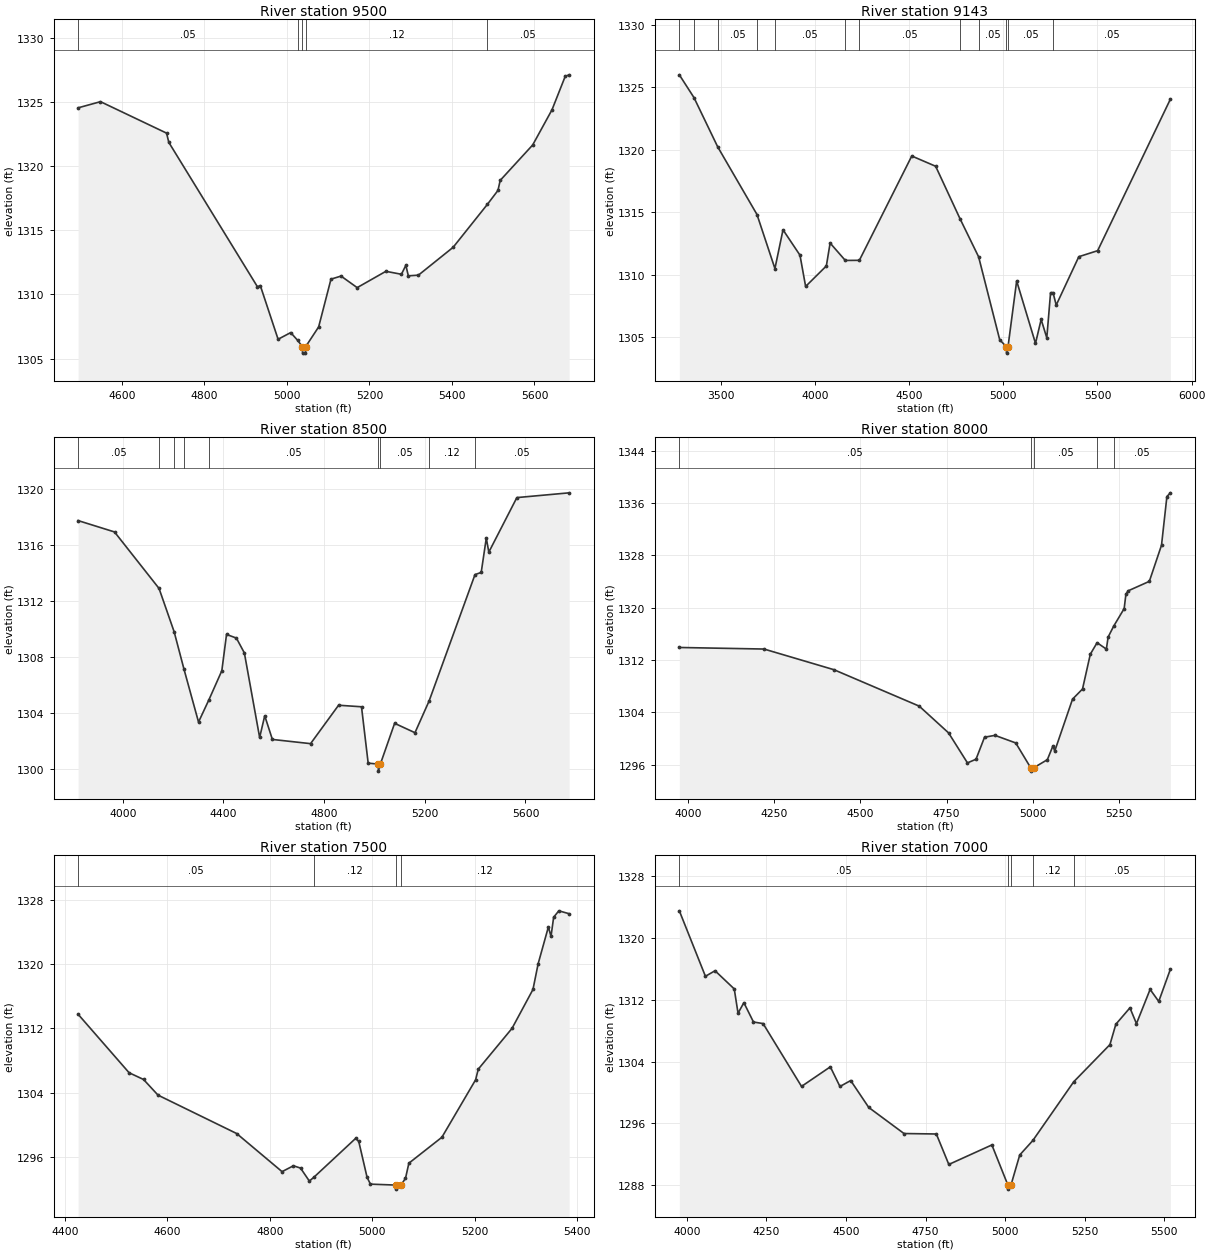
Type RM Length L Ch R = 1,9500,357,357,357
BEGIN DESCRIPTION:
HOUSE MT BRANCH 19.0
END DESCRIPTION:
XS GIS Cut Line= 3
      2746071.39     10187297.98      2746577.08     10187275.31
      2747214.45     10187026.51
#Sta/Elev= 30
  4493.8 1324.53  4548.1 1325.01  4708.3 1322.56  4713.7 1321.84  4928.5 1310.60
  4935.5 1310.69  4978.6 1306.51  5009.2 1307.03  5026.1 1306.42  5037.5 1305.93
  5038.0 1305.43  5044.9 1305.43  5045.4 1305.93  5076.9 1307.47  5106.8 1311.19
  5131.2 1311.43  5170.3 1310.53  5239.9 1311.80  5277.6 1311.57  5288.3 1312.27
  5294.3 1311.45  5318.7 1311.50  5402.9 1313.67  5486.1 1317.02  5511.6 1318.10
  5517.0 1318.88  5595.8 1321.64  5642.6 1324.38  5674.6 1326.98  5684.2 1327.10
#Mann=5,-1,0
  4493.8    0.05       0  5026.1    0.12       0  5037.5    0.05       0
  5045.4    0.12       0  5486.1    0.05       0
Bank Sta=5037.5,5045.4
Exp/Cntr=0.3,0.1

Type RM Length L Ch R = 1,9143,643,643,643
BEGIN DESCRIPTION:
HOUSE MT BRANCH 18.0
END DESCRIPTION:
XS GIS Cut Line= 3
      2745035.47     10187633.77      2746754.75     10187584.00
      2747641.95     10187583.76
#Sta/Elev= 30
  3280.0 1326.00  3357.7 1324.18  3483.7 1320.24  3692.3 1314.83  3787.5 1310.51
  3830.4 1313.61  3920.5 1311.58  3950.5 1309.08  4060.5 1310.72  4080.5 1312.55
  4161.2 1311.16  4235.8 1311.17  4514.0 1319.51  4640.8 1318.69  4770.0 1314.50
  4868.9 1311.45  4980.9 1304.82  5016.9 1304.25  5017.4 1303.75  5024.9 1304.25
  5070.9 1309.52  5170.9 1304.53  5200.9 1306.44  5230.9 1304.97  5250.9 1308.58
  5264.1 1308.58  5280.9 1307.59  5400.9 1311.46  5500.9 1311.94  5887.2 1324.06
#Mann=12,-1,0
  3280.0    0.05       0  3357.7    0.12       0  3483.7    0.05       0
  3692.3    0.12       0  3787.5    0.05       0  4161.2    0.12       0
  4235.8    0.05       0  4770.0    0.12       0  4868.9    0.05       0
  5016.9    0.05       0  5024.9    0.05       0  5264.1    0.05       0
Bank Sta=5016.9,5024.9
Exp/Cntr=0.3,0.1

Type RM Length L Ch R = 1,8500,500,500,500
BEGIN DESCRIPTION:
HOUSE MT BRANCH 17.0
END DESCRIPTION:
XS GIS Cut Line= 3
      2745592.74     10188041.01      2746756.59     10188221.75
      2747521.15     10188340.98
#Sta/Elev= 30
  3822.2 1317.75  3966.9 1316.94  4143.9 1312.91  4203.9 1309.82  4243.2 1307.14
  4300.8 1303.38  4342.4 1304.98  4393.4 1307.04  4412.1 1309.63  4451.3 1309.37
  4483.0 1308.31  4543.7 1302.28  4563.9 1303.83  4594.3 1302.14  4746.1 1301.84
  4857.4 1304.58  4948.5 1304.47  4975.0 1300.45  5015.2 1300.38  5015.7 1299.88
  5023.4 1300.38  5080.1 1303.29  5161.0 1302.62  5217.3 1304.89  5399.6 1313.90
  5424.2 1314.05  5444.4 1316.50  5454.5 1315.50  5565.9 1319.39  5773.8 1319.73
#Mann=9,-1,0
  3822.2    0.05       0  4143.9    0.12       0  4203.9    0.05       0
  4243.2    0.12       0  4342.4    0.05       0  5015.2    0.05       0
  5023.4    0.05       0  5217.3    0.12       0  5399.6    0.05       0
Bank Sta=5015.2,5023.4
Exp/Cntr=0.3,0.1

Type RM Length L Ch R = 1,8000,500,500,500
BEGIN DESCRIPTION:
HOUSE MT BRANCH 16.0
END DESCRIPTION:
XS GIS Cut Line= 3
      2745756.99     10188312.48      2746714.44     10188676.76
      2747105.66     10188753.11
#Sta/Elev= 30
  3975.6 1313.92  4221.0 1313.68  4423.6 1310.52  4670.7 1304.95  4755.7 1300.86
  4810.5 1296.27  4835.3 1296.83  4860.0 1300.20  4890.2 1300.48  4950.4 1299.32
  4993.9 1295.51  4994.4 1295.01  5002.1 1295.51  5042.0 1296.76  5058.3 1298.88
  5063.4 1298.08  5115.0 1306.02  5143.9 1307.57  5166.5 1312.89  5186.1 1314.65
  5213.0 1313.67  5218.1 1315.51  5234.2 1317.18  5264.6 1319.87  5269.7 1322.08
  5276.4 1322.59  5337.5 1324.03  5372.8 1329.56  5388.4 1337.00  5398.6 1337.57
#Mann=5,-1,0
  3975.6    0.05       0  4993.9    0.05       0  5002.1    0.05       0
  5186.1    0.12       0  5234.2    0.05       0
Bank Sta=4993.9,5002.1
Exp/Cntr=0.3,0.1

Type RM Length L Ch R = 1,7500,500,500,500
BEGIN DESCRIPTION:
HOUSE MT BRANCH 15.0
END DESCRIPTION:
XS GIS Cut Line= 3
      2746105.66     10189353.12      2746624.87     10189106.98
      2747005.68     10189053.11
#Sta/Elev= 30
  4425.4 1313.76  4525.0 1306.50  4553.3 1305.66  4581.5 1303.72  4735.2 1298.95
  4823.8 1294.22  4846.0 1294.95  4859.9 1294.66  4877.1 1293.05  4885.7 1293.51
  4967.7 1298.36  4973.6 1297.97  4989.8 1293.53  4996.4 1292.67  5046.8 1292.55
  5047.3 1292.05  5055.9 1292.55  5064.9 1293.39  5071.5 1295.27  5136.0 1298.49
  5201.9 1305.63  5207.0 1306.94  5273.0 1312.01  5313.9 1316.84  5324.0 1320.03
  5344.0 1324.60  5349.1 1323.42  5354.3 1325.81  5364.4 1326.60  5384.6 1326.24
#Mann=4,-1,0
  4425.4    0.05       0  4885.7    0.12       0  5046.8    0.07       0
  5055.9    0.12       0
Bank Sta=5046.8,5055.9
Exp/Cntr=0.3,0.1

Type RM Length L Ch R = 1,7000,500,500,500
BEGIN DESCRIPTION:
HOUSE MT BRANCH 14.0
END DESCRIPTION:
XS GIS Cut Line= 3
      2745664.17     10189698.51      2746681.57     10189583.35
      2747177.06     10189427.56
#Sta/Elev= 30
  3976.1 1323.54  4058.1 1315.05  4088.3 1315.77  4148.7 1313.41  4160.6 1310.26
  4178.9 1311.63  4209.1 1309.12  4239.3 1308.92  4360.1 1300.77  4450.6 1303.31
  4480.8 1300.76  4514.6 1301.53  4571.4 1298.04  4682.1 1294.66  4783.8 1294.60
  4823.0 1290.65  4958.3 1293.18  5008.9 1287.95  5009.4 1287.45  5018.1 1287.95
  5045.9 1291.88  5087.1 1293.76  5215.5 1301.37  5329.3 1306.19  5347.9 1308.83
  5392.2 1310.96  5412.7 1308.91  5455.6 1313.35  5482.7 1311.79  5519.4 1315.98
#Mann=5,-1,0
  3976.1    0.05       0  5008.9    0.05       0  5018.1    0.05       0
  5087.1    0.12       0  5215.5    0.05       0
Bank Sta=5008.9,5018.1
Exp/Cntr=0.3,0.1