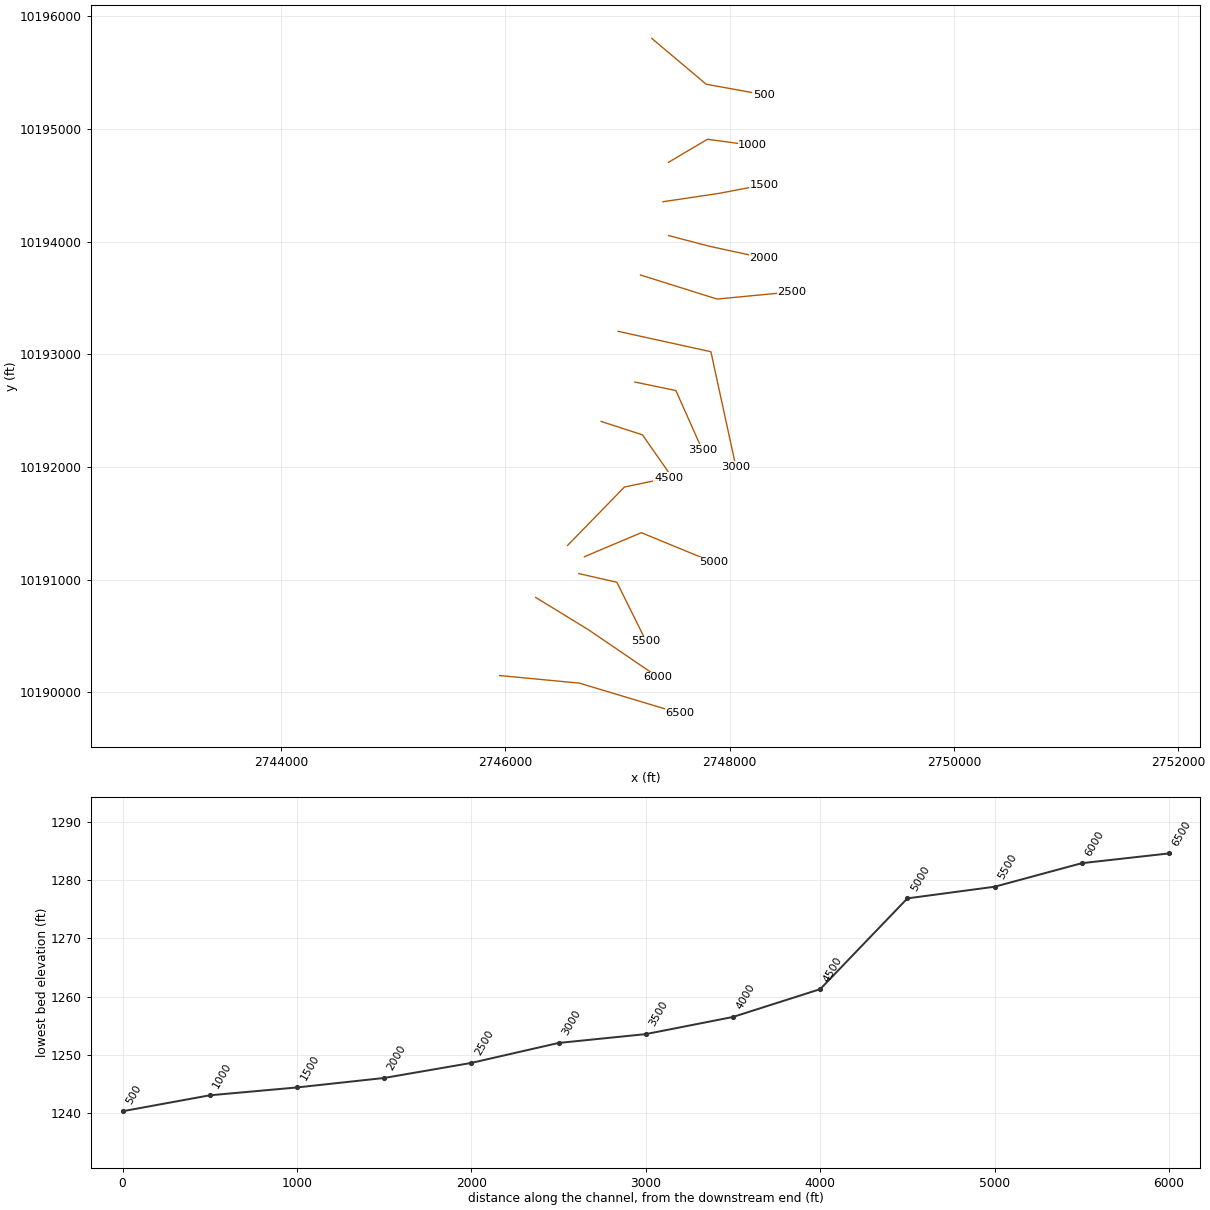
HEC-RAS study HOUSE MT BRANCH.prj: HOUSE MT BRANCH Base Level Engineering

--- HOUSE MT BRANCH.g01 (geometry) --- (continued)

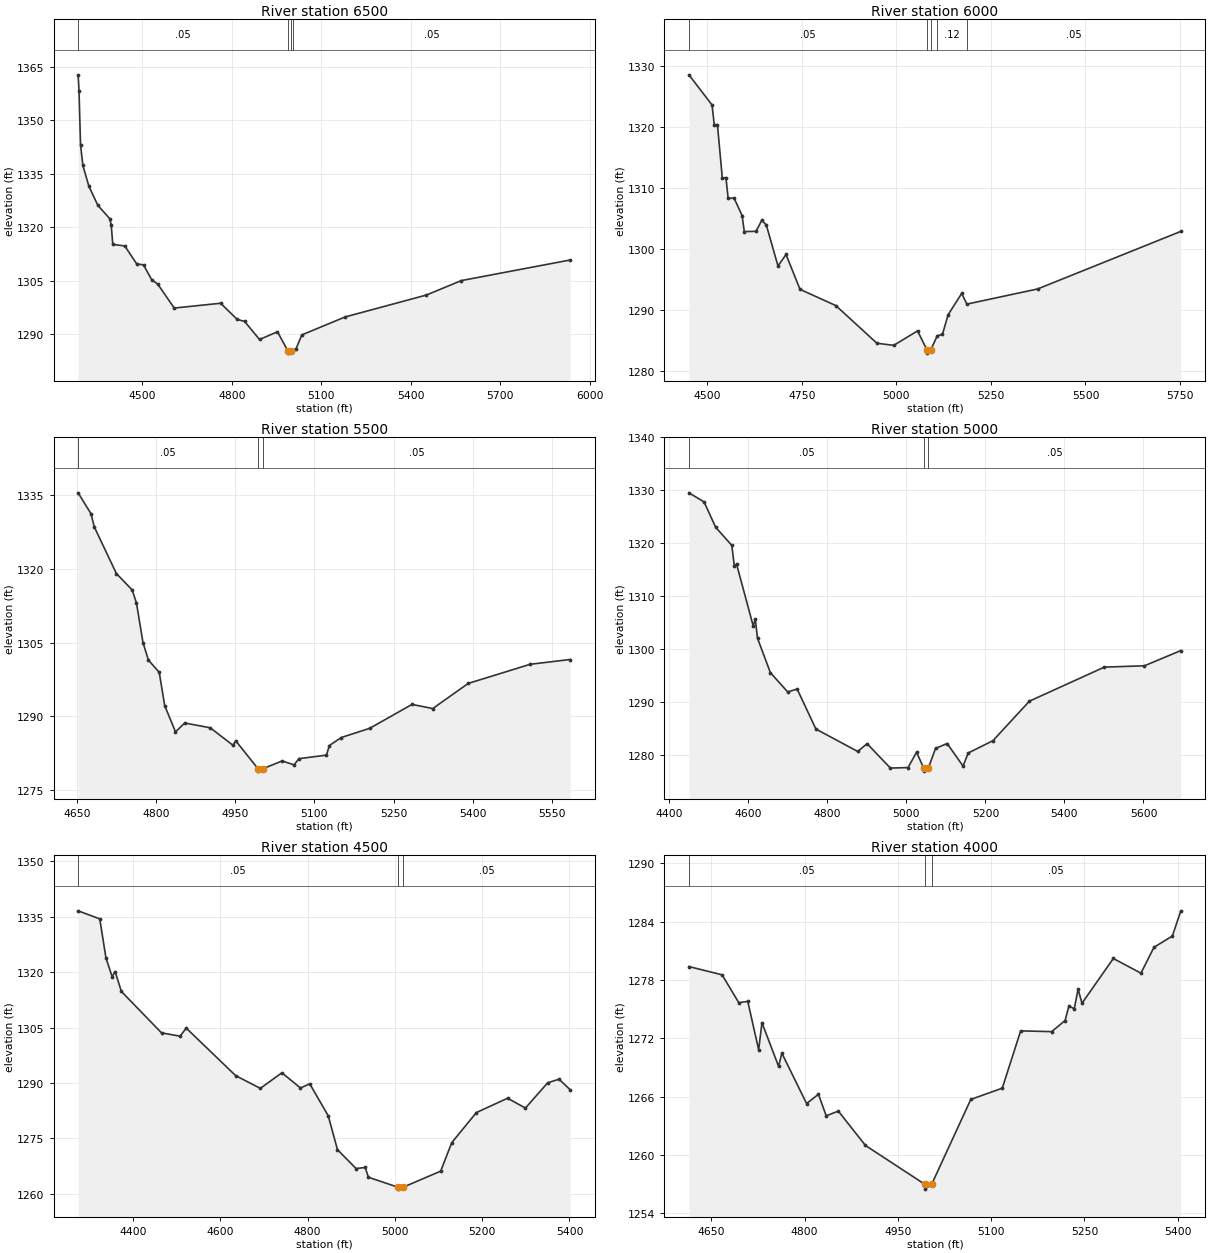
Type RM Length L Ch R = 1,6500,500,500,500
BEGIN DESCRIPTION:
HOUSE MT BRANCH 13.0
END DESCRIPTION:
XS GIS Cut Line= 3
      2745949.96     10190148.60      2746662.25     10190080.97
      2747557.45     10189812.81
#Sta/Elev= 30
  4284.5 1362.79  4287.5 1358.13  4292.5 1343.22  4300.3 1337.37  4320.4 1331.53
  4350.5 1326.15  4390.6 1322.38  4395.6 1320.59  4400.7 1315.16  4440.9 1314.73
  4481.1 1309.68  4503.8 1309.41  4531.3 1305.23  4551.4 1304.02  4606.9 1297.28
  4762.4 1298.63  4818.2 1294.08  4842.7 1293.54  4893.0 1288.45  4953.2 1290.62
  4988.8 1285.12  4989.3 1284.62  4998.1 1285.12  5005.7 1285.59  5014.6 1285.67
  5034.9 1289.74  5180.0 1294.78  5452.5 1300.93  5570.0 1305.00  5934.5 1310.77
#Mann=4,-1,0
  4284.5    0.05       0  4988.8    0.07       0  4998.1    0.05       0
  5005.7    0.05       0
Bank Sta=4988.8,4998.1
Exp/Cntr=0.3,0.1

Type RM Length L Ch R = 1,6000,500,500,500
BEGIN DESCRIPTION:
HOUSE MT BRANCH 12.0
END DESCRIPTION:
XS GIS Cut Line= 3
      2746271.40     10190841.63      2746739.50     10190556.32
      2747362.07     10190134.34
#Sta/Elev= 30
  4451.8 1328.48  4512.9 1323.54  4518.7 1320.32  4527.1 1320.33  4540.0 1311.60
  4549.6 1311.66  4555.5 1308.26  4571.0 1308.32  4592.3 1305.46  4598.1 1302.83
  4629.1 1302.87  4644.2 1304.66  4656.2 1303.94  4687.2 1297.20  4708.5 1299.08
  4745.3 1293.38  4840.1 1290.72  4948.7 1284.56  4993.1 1284.21  5056.1 1286.58
  5081.2 1283.44  5081.7 1282.94  5090.7 1283.44  5108.4 1285.79  5121.9 1286.00
  5136.9 1289.22  5172.8 1292.71  5186.5 1290.96  5373.5 1293.44  5752.1 1302.86
#Mann=5,-1,0
  4451.8    0.05       0  5081.2    0.05       0  5090.7    0.05       0
  5108.4    0.12       0  5186.5    0.05       0
Bank Sta=5081.2,5090.7
Exp/Cntr=0.3,0.1

Type RM Length L Ch R = 1,5500,500,500,500
BEGIN DESCRIPTION:
HOUSE MT BRANCH 11.0
END DESCRIPTION:
XS GIS Cut Line= 3
      2746655.66     10191053.12      2746995.11     10190976.42
      2747255.68     10190453.11
#Sta/Elev= 30
  4652.0 1335.39  4676.2 1331.18  4682.8 1328.43  4724.5 1319.01  4754.5 1315.66
  4762.6 1313.02  4775.0 1304.97  4785.3 1301.43  4805.8 1298.93  4816.1 1292.20
  4836.6 1286.86  4854.1 1288.66  4902.4 1287.69  4945.6 1284.14  4950.7 1285.06
  4993.0 1279.39  4993.5 1278.89  5002.5 1279.39  5038.9 1280.96  5061.3 1280.16
  5070.7 1281.42  5122.8 1282.14  5128.4 1284.09  5150.8 1285.71  5204.8 1287.58
  5285.1 1292.44  5324.3 1291.59  5391.5 1296.69  5509.0 1300.58  5584.6 1301.55
#Mann=3,-1,0
  4652.0    0.05       0  4993.0    0.05       0  5002.5    0.05       0
Bank Sta=4993,5002.5
Exp/Cntr=0.3,0.1

Type RM Length L Ch R = 1,5000,500,500,500
BEGIN DESCRIPTION:
HOUSE MT BRANCH 10.0
END DESCRIPTION:
XS GIS Cut Line= 3
      2746705.70     10191203.12      2747212.92     10191416.30
      2747855.72     10191153.10
#Sta/Elev= 30
  4449.8 1329.52  4488.1 1327.80  4517.3 1323.02  4558.3 1319.58  4564.8 1315.59
  4570.2 1316.07  4612.3 1304.38  4617.7 1305.64  4623.3 1302.02  4655.9 1295.52
  4699.8 1291.86  4723.6 1292.42  4771.1 1284.85  4876.9 1280.61  4900.7 1282.08
  4959.6 1277.47  5004.2 1277.56  5025.8 1280.46  5044.4 1277.39  5044.9 1276.89
  5055.3 1277.39  5073.8 1281.19  5103.2 1282.11  5143.5 1277.85  5156.6 1280.32
  5219.1 1282.65  5311.4 1290.12  5501.0 1296.56  5602.5 1296.81  5694.6 1299.69
#Mann=3,-1,0
  4449.8    0.05       0  5044.4    0.05       0  5055.3    0.05       0
Bank Sta=5044.4,5055.3
Exp/Cntr=0.3,0.1

Type RM Length L Ch R = 1,4500,500,500,500
BEGIN DESCRIPTION:
HOUSE MT BRANCH 9.0
END DESCRIPTION:
XS GIS Cut Line= 3
      2746555.65     10191303.08      2747062.83     10191821.71
      2747455.68     10191903.11
#Sta/Elev= 30
  4274.6 1336.63  4324.2 1334.44  4338.3 1323.89  4352.4 1318.81  4359.4 1320.19
  4373.6 1314.81  4465.6 1303.59  4508.0 1302.69  4522.2 1304.87  4635.3 1292.02
  4691.9 1288.56  4741.3 1292.78  4783.8 1288.67  4805.1 1289.79  4847.5 1281.11
  4868.6 1271.96  4911.1 1266.86  4932.2 1267.14  4939.4 1264.50  5007.6 1261.78
  5008.1 1261.28  5018.6 1261.78  5105.0 1266.15  5130.3 1273.86  5186.7 1282.01
  5258.2 1285.89  5299.1 1283.23  5350.1 1290.08  5376.1 1291.04  5401.2 1288.23
#Mann=3,-1,0
  4274.6    0.05       0  5007.6    0.03       0  5018.6    0.05       0
Bank Sta=5007.6,5018.6
Exp/Cntr=0.3,0.1

Type RM Length L Ch R = 1,4000,500,500,500
BEGIN DESCRIPTION:
HOUSE MT BRANCH 8.0
END DESCRIPTION:
XS GIS Cut Line= 3
      2746855.68     10192403.11      2747222.88     10192284.47
      2747455.71     10191953.08
#Sta/Elev= 30
  4614.1 1279.38  4667.4 1278.53  4694.2 1275.67  4708.7 1275.80  4726.2 1270.82
  4731.5 1273.61  4758.2 1269.13  4763.5 1270.47  4803.3 1265.30  4822.3 1266.25
  4834.8 1264.04  4854.3 1264.52  4897.9 1260.99  4993.3 1257.00  4993.8 1256.50
  5004.4 1257.00  5067.3 1265.72  5117.9 1266.88  5147.5 1272.77  5197.2 1272.69
  5218.9 1273.83  5225.0 1275.31  5233.7 1275.05  5239.8 1277.05  5246.1 1275.61
  5296.5 1280.21  5340.9 1278.70  5361.8 1281.36  5391.4 1282.52  5405.0 1285.11
#Mann=3,-1,0
  4614.1    0.05       0  4993.3    0.05       0  5004.4    0.05       0
Bank Sta=4993.3,5004.4
Exp/Cntr=0.3,0.1

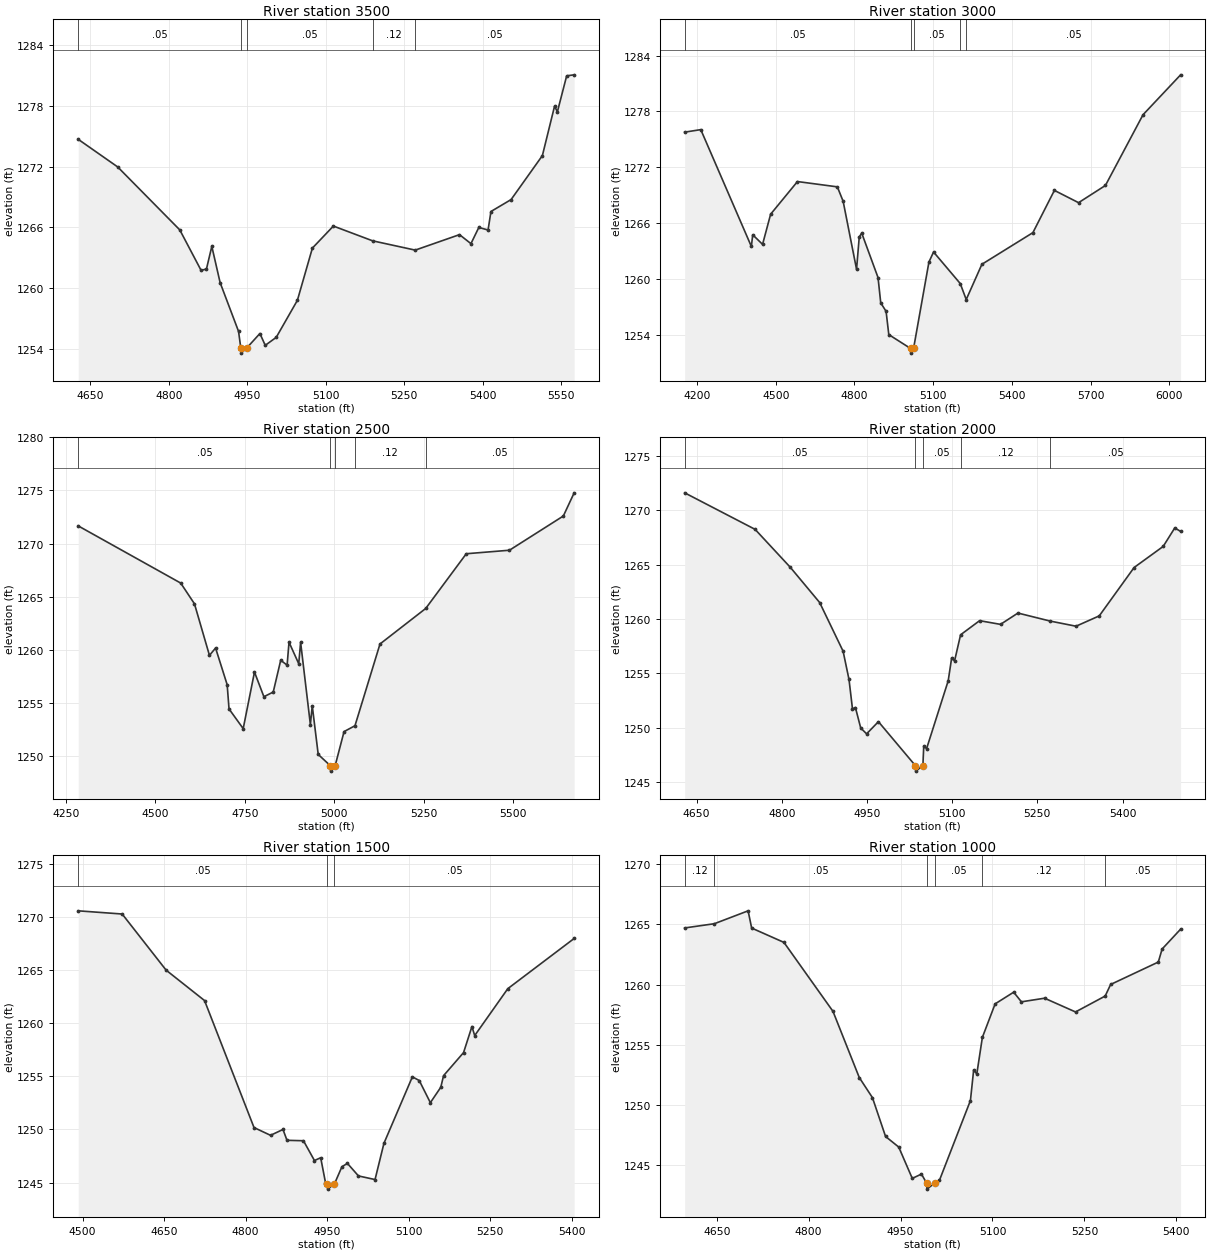
Type RM Length L Ch R = 1,3500,500,500,500
BEGIN DESCRIPTION:
HOUSE MT BRANCH 7.0
END DESCRIPTION:
XS GIS Cut Line= 3
      2747155.65     10192753.12      2747521.12     10192677.58
      2747755.67     10192153.14
#Sta/Elev= 30
  4626.8 1274.70  4702.2 1271.97  4820.9 1265.74  4861.7 1261.73  4871.9 1261.88
  4882.1 1264.11  4898.0 1260.52  4933.2 1255.70  4937.5 1254.05  4938.0 1253.55
  4948.7 1254.05  4974.0 1255.49  4984.2 1254.32  5005.2 1255.11  5045.6 1258.77
  5074.3 1263.94  5114.4 1266.12  5189.3 1264.66  5270.8 1263.74  5355.4 1265.27
  5377.3 1264.38  5392.3 1265.98  5410.0 1265.73  5415.5 1267.56  5454.0 1268.74
  5513.8 1273.09  5537.0 1277.97  5542.5 1277.43  5560.2 1280.98  5574.5 1281.08
#Mann=5,-1,0
  4626.8    0.05       0  4937.5    0.03       0  4948.7    0.05       0
  5189.3    0.12       0  5270.8    0.05       0
Bank Sta=4937.5,4948.7
Exp/Cntr=0.3,0.1

Type RM Length L Ch R = 1,3000,500,500,500
BEGIN DESCRIPTION:
HOUSE MT BRANCH 6.0
END DESCRIPTION:
XS GIS Cut Line= 3
      2747005.66     10193203.12      2747833.32     10193022.22
      2748055.69     10192003.09
#Sta/Elev= 30
  4152.8 1275.78  4214.2 1276.05  4407.0 1263.49  4412.1 1264.75  4449.7 1263.72
  4480.4 1266.96  4582.7 1270.47  4734.7 1269.90  4756.8 1268.35  4807.9 1261.04
  4818.2 1264.52  4827.6 1264.93  4889.8 1260.15  4900.1 1257.43  4920.5 1256.52
  4930.8 1254.02  5013.9 1252.53  5014.4 1252.03  5025.2 1252.53  5083.8 1261.82
  5101.4 1262.90  5203.1 1259.51  5225.9 1257.79  5285.7 1261.58  5480.1 1264.98
  5562.0 1269.52  5654.1 1268.20  5756.5 1270.05  5899.8 1277.65  6043.1 1281.94
#Mann=5,-1,0
  4152.8    0.05       0  5013.9    0.03       0  5025.2    0.05       0
  5203.1    0.12       0  5225.9    0.05       0
Bank Sta=5013.9,5025.2
Exp/Cntr=0.3,0.1

Type RM Length L Ch R = 1,2500,500,500,500
BEGIN DESCRIPTION:
HOUSE MT BRANCH 5.0
END DESCRIPTION:
XS GIS Cut Line= 3
      2747205.69     10193703.11      2747888.34     10193489.48
      2748555.71     10193553.11
#Sta/Elev= 30
  4284.7 1271.67  4571.1 1266.29  4609.5 1264.34  4651.4 1259.49  4668.5 1260.18
  4700.9 1256.73  4706.1 1254.45  4745.7 1252.60  4777.2 1257.92  4803.5 1255.60
  4829.6 1256.04  4850.5 1259.03  4868.4 1258.57  4873.7 1260.73  4900.9 1258.70
  4906.1 1260.72  4933.4 1252.98  4938.6 1254.75  4955.3 1250.17  4989.5 1249.10
  4990.0 1248.60  5002.5 1249.10  5027.5 1252.32  5058.0 1252.87  5127.9 1260.56
  5255.6 1263.90  5369.0 1269.05  5489.6 1269.38  5640.2 1272.60  5670.4 1274.78
#Mann=5,-1,0
  4284.7    0.05       0  4989.5    0.05       0  5002.5    0.05       0
  5058.0    0.12       0  5255.6    0.05       0
Bank Sta=4989.5,5002.5
Exp/Cntr=0.3,0.1

Type RM Length L Ch R = 1,2000,500,500,500
BEGIN DESCRIPTION:
HOUSE MT BRANCH 4.0
END DESCRIPTION:
XS GIS Cut Line= 3
      2747455.71     10194053.10      2747814.75     10193959.26
      2748305.71     10193853.11
#Sta/Elev= 30
  4628.9 1271.61  4752.9 1268.25  4814.9 1264.76  4866.6 1261.52  4907.9 1257.04
  4918.3 1254.44  4924.4 1251.74  4929.6 1251.86  4938.9 1249.98  4949.3 1249.44
  4970.1 1250.56  5035.3 1246.51  5035.8 1246.01  5048.4 1246.51  5049.9 1248.28
  5055.0 1248.09  5093.0 1254.32  5099.1 1256.43  5104.2 1256.15  5114.8 1258.55
  5148.3 1259.85  5185.1 1259.51  5215.8 1260.55  5272.8 1259.81  5318.1 1259.34
  5359.0 1260.29  5420.4 1264.74  5471.6 1266.68  5492.0 1268.38  5502.3 1268.06
#Mann=5,-1,0
  4628.9    0.05       0  5035.3    0.03       0  5048.4    0.05       0
  5114.8    0.12       0  5272.8    0.05       0
Bank Sta=5035.3,5048.4
Exp/Cntr=0.3,0.1

Type RM Length L Ch R = 1,1500,500,500,500
BEGIN DESCRIPTION:
HOUSE MT BRANCH 3.0
END DESCRIPTION:
XS GIS Cut Line= 3
      2747405.66     10194353.11      2747908.25     10194427.74
      2748305.67     10194503.11
#Sta/Elev= 30
  4491.9 1270.55  4572.8 1270.25  4653.7 1264.97  4724.4 1262.11  4815.4 1250.17
  4845.8 1249.44  4868.7 1249.99  4876.1 1248.97  4906.4 1248.93  4926.6 1247.07
  4938.1 1247.33  4946.9 1245.00  4950.4 1244.88  4950.9 1244.38  4963.5 1244.88
  4977.2 1246.49  4987.3 1246.80  5007.6 1245.62  5038.1 1245.28  5054.5 1248.69
  5106.8 1254.94  5119.5 1254.59  5139.9 1252.51  5159.1 1253.96  5164.2 1255.05
  5201.0 1257.22  5216.4 1259.67  5221.5 1258.82  5282.4 1263.23  5404.5 1267.95
#Mann=3,-1,0
  4491.9    0.05       0  4950.4    0.03       0  4963.5    0.05       0
Bank Sta=4950.4,4963.5
Exp/Cntr=0.3,0.1

Type RM Length L Ch R = 1,1000,500,500,500
BEGIN DESCRIPTION:
HOUSE MT BRANCH 2.0
END DESCRIPTION:
XS GIS Cut Line= 3
      2747455.72     10194703.13      2747802.30     10194907.41
      2748205.66     10194853.12
#Sta/Elev= 30
  4597.7 1264.70  4646.1 1265.05  4701.2 1266.12  4707.0 1264.69  4759.7 1263.50
  4839.7 1257.78  4882.6 1252.29  4904.1 1250.62  4925.5 1247.40  4947.0 1246.52
  4969.1 1243.92  4984.1 1244.28  4992.5 1243.53  4993.0 1243.03  5005.6 1243.53
  5013.5 1243.77  5064.0 1250.38  5069.3 1252.93  5074.4 1252.58  5083.5 1255.62
  5104.3 1258.40  5134.6 1259.37  5147.2 1258.57  5185.0 1258.87  5235.5 1257.73
  5283.9 1259.05  5292.8 1260.01  5370.6 1261.87  5376.8 1262.95  5407.0 1264.60
#Mann=6,-1,0
  4597.7    0.12       0  4646.1    0.05       0  4992.5    0.05       0
  5005.6    0.05       0  5083.5    0.12       0  5283.9    0.05       0
Bank Sta=4992.5,5005.6
Exp/Cntr=0.3,0.1

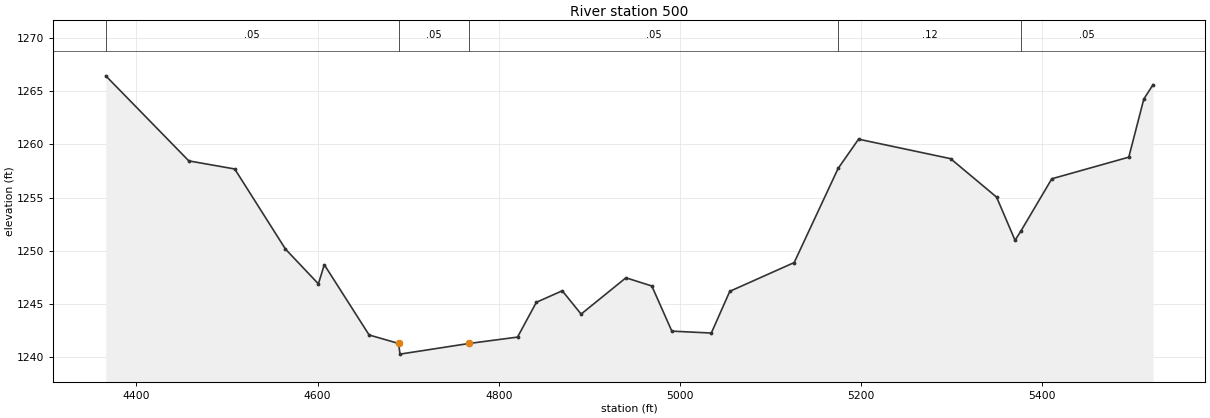
Type RM Length L Ch R = 1,500,0,0,0
BEGIN DESCRIPTION:
HOUSE MT BRANCH 1.0
END DESCRIPTION:
XS GIS Cut Line= 3
      2747305.69     10195803.10      2747791.39     10195395.76
      2748305.71     10195303.11
#Sta/Elev= 30
  4366.1 1266.43  4457.8 1258.44  4508.5 1257.68  4564.5 1250.16  4600.9 1246.89
  4607.4 1248.69  4656.9 1242.09  4689.5 1241.29  4691.0 1240.29  4767.2 1241.29
  4820.8 1241.89  4841.6 1245.16  4870.2 1246.24  4891.0 1244.05  4940.5 1247.46
  4969.1 1246.69  4991.2 1242.45  5034.8 1242.27  5055.2 1246.19  5126.3 1248.89
  5174.8 1257.73  5197.4 1260.48  5299.0 1258.65  5349.8 1255.04  5370.2 1250.98
  5377.0 1251.90  5410.8 1256.76  5495.8 1258.79  5512.4 1264.25  5522.6 1265.60
#Mann=5,-1,0
  4366.1    0.05       0  4689.5    0.05       0  4767.2    0.05       0
  5174.8    0.12       0  5377.0    0.05       0
Bank Sta=4689.5,4767.2
Exp/Cntr=0.3,0.1

Chan Stop Cuts=-1