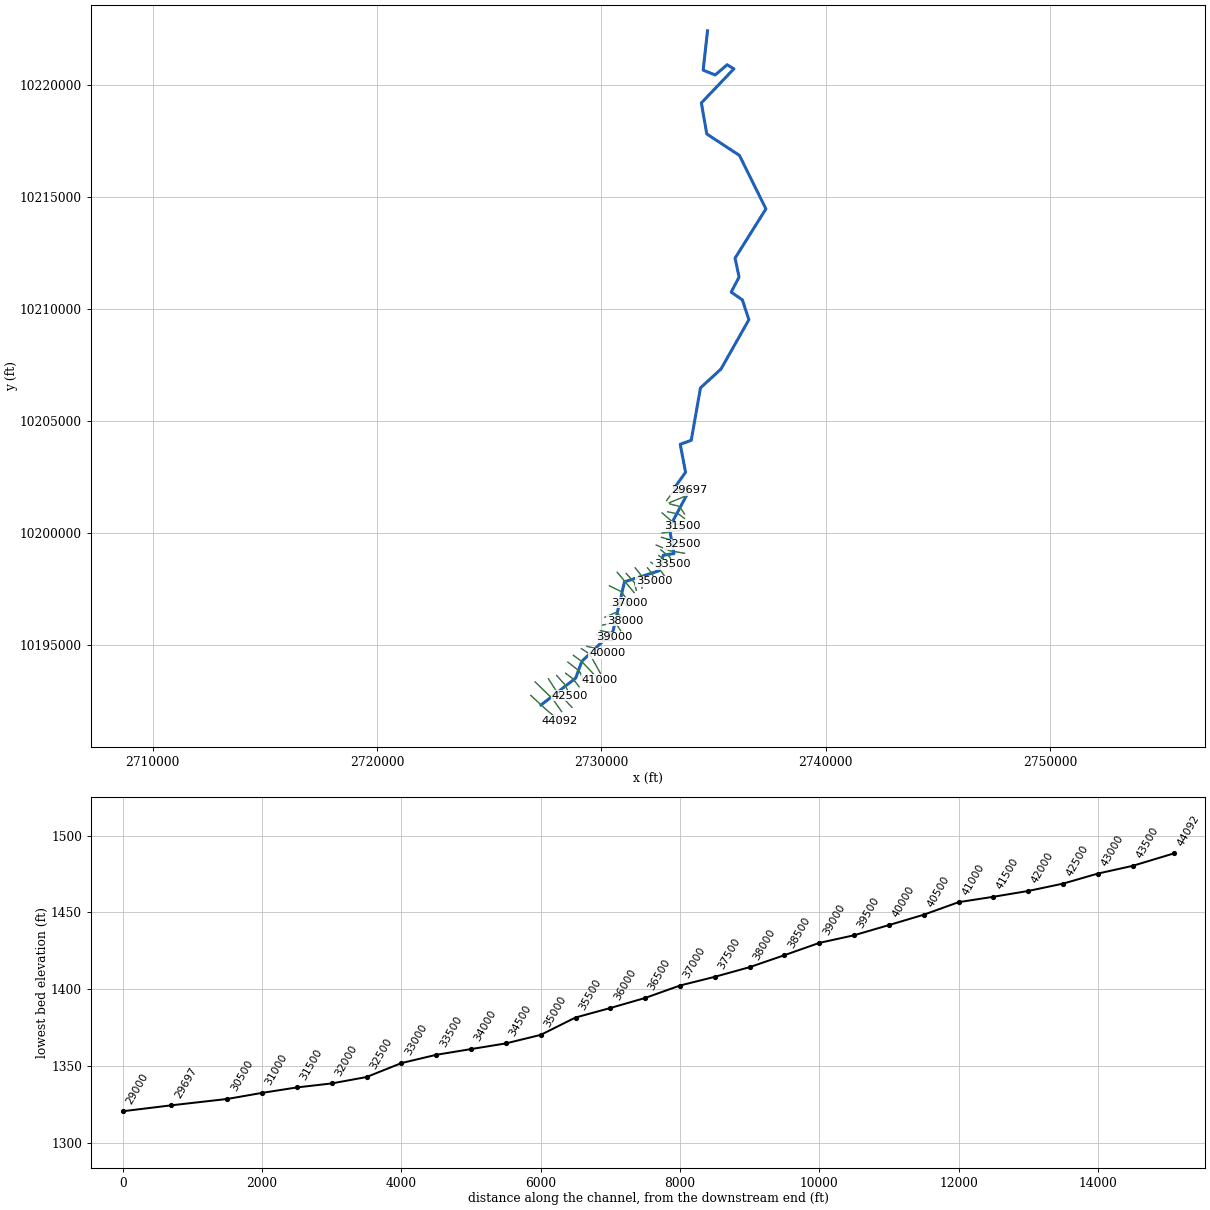
--- LANG CREEK.prj (project) ---

Proj Title=LANG CREEK Base Level Engineering
Current Plan=p01
Default Exp/Contr=0.3,0.1
English Units
Geom File=g01
Flow File=f01
Plan File=p01
Y Axis Title=Elevation
X Axis Title(PF)=Main Channel Distance
X Axis Title(XS)=Station
BEGIN DESCRIPTION:
LANG CREEK
END DESCRIPTION:
DSS Export Rating Curves= 0
DSS Export Rating Curve Sorted= 0
DSS Export Volume Flow Curves= 0
DXF OffsetX= 0
DXF OffsetY= 0
DXF ScaleX= 1
DXF ScaleY= 10

--- LANG CREEK.p01 (plan) ---

Plan Title=Multiple Run
Short Identifier=Multiple
Geom File=g01
Flow File=f01
Subcritical Flow
K Sum by GR= 0
Std Step Tol= 0.01
Critical Tol= 0.01
Num of Std Step Trials= 20
Max Error Tol= 0.3
Flow Tol Ratio= 0.001
Split Flow NTrial= 30
Split Flow Tol= 0.02
Split Flow Ratio= 0.02
Log Output Level= 0
Friction Slope Method= 1
Unsteady Friction Slope Method= 2
Unsteady Bridges Friction Slope Method= 1
Parabolic Critical Depth
Global Vel Dist=  1 , 1 , 1
Global Log Level= 0
CheckData=True
Encroach Param= -1, 0, 0, 0
BEGIN DESCRIPTION:
Multiple Run
END DESCRIPTION:

--- LANG CREEK.f01 (steady flow) ---

Flow Title=Multiple
Program Version=4.10
Number of Profiles= 7
Profile Names=10-year,25-year,50-year,1pct_min,100-year,1pct_plu,500-year
River Rch & RM=LANG CREEK,Reach-1         ,44092
     501     820    1090     794    1459    2683    2007
River Rch & RM=LANG CREEK,Reach-1         ,37500
     841    1435    1983    1346    2722    5503    3776
River Rch & RM=LANG CREEK,Reach-1         ,28000
    1245    2188    2965    1916    4120    8861    5713
River Rch & RM=LANG CREEK,Reach-1         ,17000
    1319    2327    3169    2042    4414    9544    6120
River Rch & RM=LANG CREEK,Reach-1         ,15000
    1593    2843    3988    2564    5600   12231    7761
River Rch & RM=LANG CREEK,Reach-1         ,10500
    1645    2945    4145    2652    5833   12829    8094
River Rch & RM=LANG CREEK,Reach-1         ,9000
    2018    3648    5460    3541    7760   17003   10757
River Rch & RM=LANG CREEK,Reach-1         ,6500
    3215    5995    9836    6514   14224   31057   19488
Boundary for River Rch & Prof#=LANG CREEK,Reach-1         , 1
Up Type= 0
Dn Type= 3
Dn Slope=0.005
Boundary for River Rch & Prof#=LANG CREEK,Reach-1         , 2
Up Type= 0
Dn Type= 3
Dn Slope=0.005
Boundary for River Rch & Prof#=LANG CREEK,Reach-1         , 3
Up Type= 0
Dn Type= 3
Dn Slope=0.005
Boundary for River Rch & Prof#=LANG CREEK,Reach-1         , 4
Up Type= 0
Dn Type= 3
Dn Slope=0.005
Boundary for River Rch & Prof#=LANG CREEK,Reach-1         , 5
Up Type= 0
Dn Type= 3
Dn Slope=0.005
Boundary for River Rch & Prof#=LANG CREEK,Reach-1         , 6
Up Type= 0
Dn Type= 3
Dn Slope=0.005
Boundary for River Rch & Prof#=LANG CREEK,Reach-1         , 7
Up Type= 0
Dn Type= 3
Dn Slope=0.005
DSS Import GetInterval= 0
DSS Import GetPeak= 0
DSS Import FillOption= 0

--- LANG CREEK.g01 (geometry) ---

Geom Title=Existing Conditions
Program Version=4.10

River Reach=LANG CREEK      ,Reach-1
Reach XY= 30
      2727306.25       10192338.      2728852.75       10193536.
      2729126.25       10194283.      2730514.25       10195614.
      2731029.25       10197830.        2732561.       10198317.
      2732757.25       10199015.       2733237.5       10199090.
        2733024.       10200236.      2733818.75       10201726.
        2733248.       10202007.        2733752.       10202715.
       2733514.5       10203963.      2734004.25       10204138.
      2734416.75       10206476.      2735331.25       10207315.
        2736575.       10209517.      2736284.25       10210402.
       2735784.5       10210742.      2736137.25       10211416.
      2735959.25       10212261.       2737334.5       10214455.
        2736152.       10216841.       2734697.5       10217795.
        2734456.       10219179.       2735907.5       10220700.
      2735603.25       10220880.      2735074.75       10220425.
      2734535.75       10220640.      2734731.25       10222391.

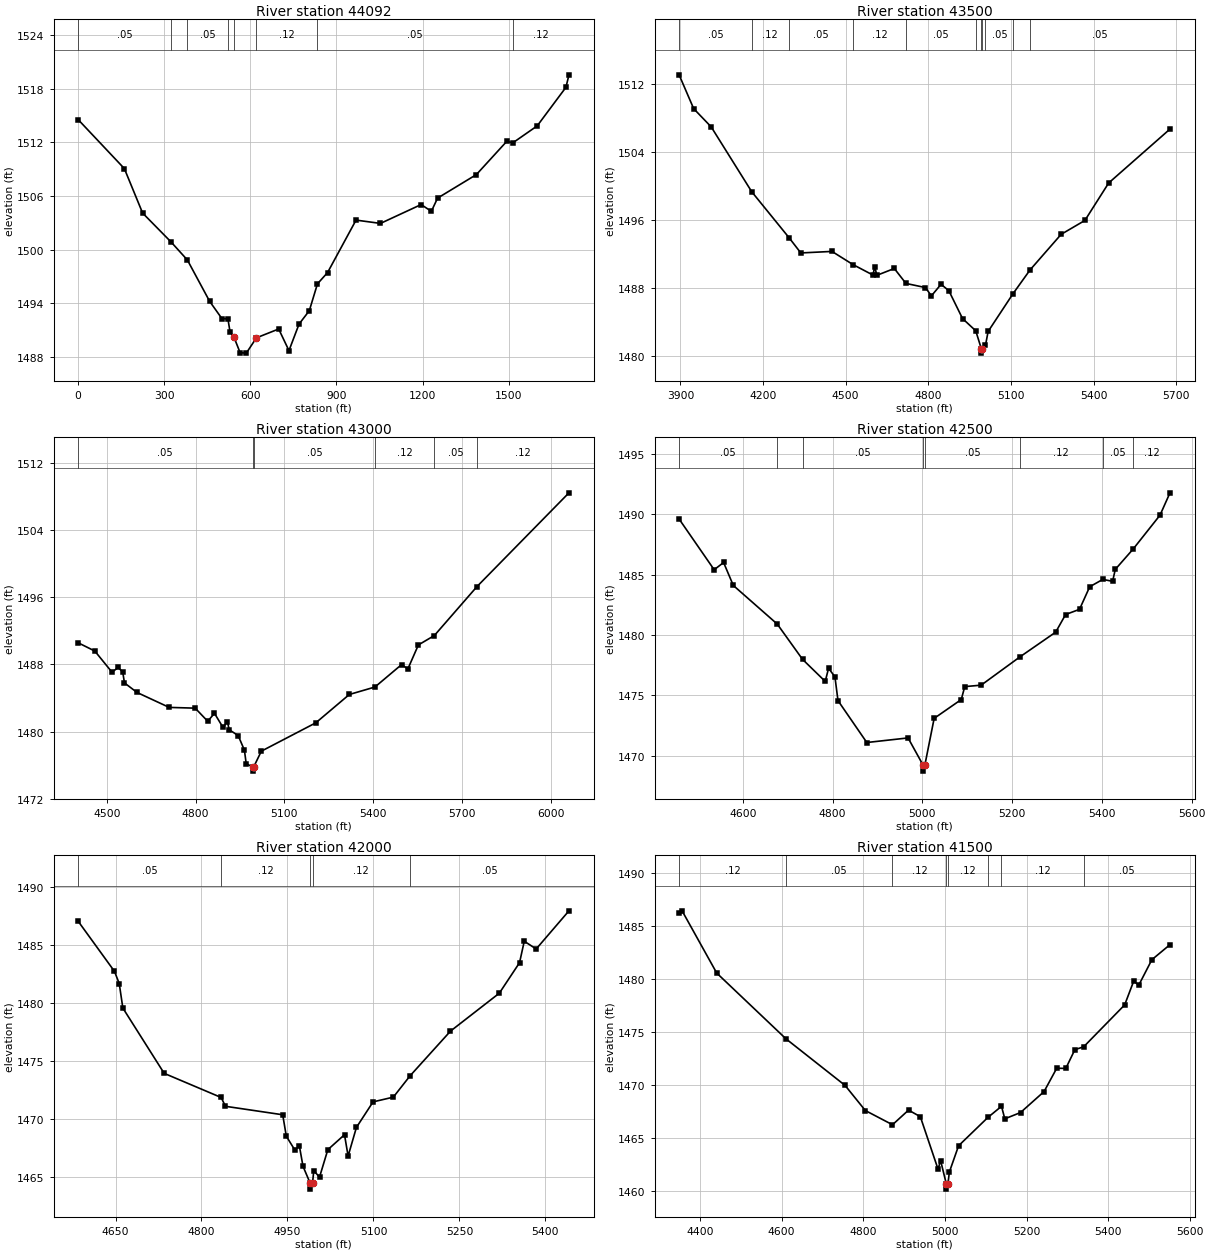
Type RM Length L Ch R = 1 ,44092   ,592,592,592
BEGIN DESCRIPTION:
LANG CREEK 86.0
END DESCRIPTION:
XS GIS Cut Line= 3
        2726852.     10192767.17      2727511.72     10192158.88
      2728131.52     10191632.89
#Sta/Elev= 30
       0 1514.55   161.2 1509.06   224.7 1504.09   323.9 1500.85   380.6 1498.84
   458.3 1494.21   500.8 1492.29   521.9 1492.25   529.2  1490.8   543.4 1490.17
   564.3 1488.47   585.9 1488.42   621.1 1490.13   698.7 1491.12   734.5  1488.7
   769.6 1491.67   805.4 1493.17   833.7 1496.17   868.9 1497.43   968.1  1503.3
  1053.2 1502.93  1194.9 1505.04  1230.4 1504.28  1252.1 1505.76  1387.2 1508.39
  1492.8  1512.1  1514.6 1511.95  1599.1 1513.84  1699.1 1518.15  1709.7 1519.55
#Mann= 8 ,-1 , 0
       0     .05       0   323.9     .12       0   380.6     .05       0
   521.9     .12       0   543.4     .07       0   621.1     .12       0
   833.7     .05       0  1514.6     .12       0
Bank Sta=543.4,621.1
XS Rating Curve= 0 ,0
Exp/Cntr=0.3,0.1

Type RM Length L Ch R = 1 ,43500   ,500,500,500
BEGIN DESCRIPTION:
LANG CREEK 85.0
END DESCRIPTION:
XS GIS Cut Line= 3
      2727046.12     10193368.16      2727838.52     10192598.59
        2728227.     10192044.02
#Sta/Elev= 30
  3895.4  1513.1  3948.2 1509.12  4011.8 1506.97    4159 1499.33  4294.1 1493.93
  4337.2 1492.12  4450.3  1492.3  4526.5 1490.75  4598.8 1489.52  4605.7 1490.52
  4612.9 1489.48  4676.5 1490.29  4718.7 1488.53  4789.7 1488.04    4811 1487.06
  4846.2 1488.43  4874.5 1487.67  4924.2 1484.39  4972.1 1482.95  4992.5 1480.82
  4992.8 1480.32  4996.5 1480.82  5007.5 1481.25    5017 1482.87  5107.8 1487.34
  5169.2 1490.12    5282 1494.31  5368.3 1495.95  5454.6 1500.36  5677.1 1506.71
#Mann= 11 ,-1 , 0
  3895.4     .05       0    4159     .12       0  4294.1     .05       0
  4526.5     .12       0  4718.7     .05       0  4972.1     .12       0
  4992.5     .07       0  4996.5     .12       0  5007.5     .05       0
  5107.8     .12       0  5169.2     .05       0
Bank Sta=4992.5,4996.5
XS Rating Curve= 0 ,0
Exp/Cntr=0.3,0.1

Type RM Length L Ch R = 1 ,43000   ,500,500,500
BEGIN DESCRIPTION:
LANG CREEK 84.0
END DESCRIPTION:
XS GIS Cut Line= 3
      2727636.25      10193510.7      2727959.61      10193008.5
      2728687.33     10192235.16
#Sta/Elev= 30
  4402.7 1490.59  4459.3  1489.6  4517.3 1487.08  4538.4 1487.64  4553.6 1487.09
  4559.5  1485.8    4602 1484.66  4710.7 1482.88  4798.5 1482.79  4840.8 1481.23
  4863.7 1482.17  4892.3 1480.51  4907.5 1481.18  4913.4 1480.22  4943.8 1479.52
  4964.9 1477.78  4970.9 1476.18  4992.3 1475.78  4992.5 1475.28  4996.3 1475.78
  5022.1 1477.66  5206.2 1481.04  5319.5 1484.42  5406.1 1485.31  5496.3 1487.99
  5517.3 1487.46  5552.9 1490.33  5606.9 1491.45    5751 1497.29  6061.9 1508.47
#Mann= 6 ,-1 , 0
  4402.7     .05       0  4992.3     .05       0  4996.3     .05       0
  5406.1     .12       0  5606.9     .05       0    5751     .12       0
Bank Sta=4992.3,4996.3
XS Rating Curve= 0 ,0
Exp/Cntr=0.3,0.1

Type RM Length L Ch R = 1 ,42500   ,500,500,500
BEGIN DESCRIPTION:
LANG CREEK 83.0
END DESCRIPTION:
XS GIS Cut Line= 3
      2728005.66     10193653.14      2728369.16     10193251.51
      2728605.69     10192753.09
#Sta/Elev= 30
  4458.3 1489.61  4536.4 1485.41  4557.4 1486.01    4579 1484.11  4676.9 1480.91
  4733.2 1477.99  4783.8 1476.16  4791.2 1477.25  4805.4 1476.54  4812.2 1474.57
  4876.4  1471.1  4968.3 1471.48  5001.7 1469.23  5001.9 1468.73  5005.7 1469.23
  5026.4  1473.1  5086.8 1474.66  5094.6 1475.73  5131.1 1475.85  5217.4 1478.19
  5297.1 1480.24  5319.2  1481.7  5350.2 1482.13  5372.9    1484  5402.1 1484.61
  5423.9 1484.45  5429.9 1485.44  5469.8 1487.13  5529.5 1489.93  5551.7 1491.78
#Mann= 8 ,-1 , 0
  4458.3     .05       0  4676.9     .12       0  4733.2     .05       0
  5001.7     .05       0  5005.7     .05       0  5217.4     .12       0
  5402.1     .05       0  5469.8     .12       0
Bank Sta=5001.7,5005.7
XS Rating Curve= 0 ,0
Exp/Cntr=0.3,0.1

Type RM Length L Ch R = 1 ,42000   ,500,500,500
BEGIN DESCRIPTION:
LANG CREEK 82.0
END DESCRIPTION:
XS GIS Cut Line= 3
      2728405.71     10193753.09      2728737.44     10193503.24
       2729005.7     10193153.09
#Sta/Elev= 30
  4584.7 1487.05  4648.2 1482.72  4656.5 1481.67  4662.8 1479.56  4734.9 1473.93
  4834.3 1471.85  4841.8 1471.09  4941.7 1470.36    4948 1468.51  4962.6 1467.34
  4970.9 1467.64  4977.1 1465.92  4989.7 1464.45    4990 1463.95  4993.7 1464.45
  4995.9 1465.55  5005.9 1464.98  5020.4 1467.35  5049.5 1468.64  5055.8  1466.8
  5070.3 1469.27  5099.3 1471.47  5134.7 1471.88  5164.1 1473.73  5234.4 1477.57
  5319.6 1480.84  5354.9 1483.47  5363.1 1485.32  5383.9 1484.65  5441.1 1487.94
#Mann= 5 ,-1 , 0
  4584.7     .05       0  4834.3     .12       0  4989.7     .07       0
  4993.7     .12       0  5164.1     .05       0
Bank Sta=4989.7,4993.7
XS Rating Curve= 0 ,0
Exp/Cntr=0.3,0.1

Type RM Length L Ch R = 1 ,41500   ,500,500,500
BEGIN DESCRIPTION:
LANG CREEK 81.0
END DESCRIPTION:
XS GIS Cut Line= 3
      2728505.66     10194253.13      2729016.97     10193850.02
      2729255.69     10193353.09
#Sta/Elev= 30
  4348.9 1486.21  4356.2 1486.41  4441.1 1480.54  4610.7 1474.34  4755.4 1469.95
  4805.1 1467.58  4871.6 1466.24  4910.9 1467.62  4939.8    1467  4983.1 1462.06
  4989.5 1462.85  5003.4 1460.67  5003.6 1460.17  5007.4 1460.67  5010.9 1461.78
  5033.5 1464.26  5105.3 1466.93  5138.6 1467.98  5146.7  1466.8  5185.2 1467.39
  5242.9 1469.37  5273.9 1471.57  5296.1 1471.55  5318.3 1473.32  5339.9 1473.59
  5440.3 1477.54  5462.5 1479.79  5474.8  1479.4  5506.9  1481.8  5551.3 1483.22
#Mann= 8 ,-1 , 0
  4348.9     .12       0  4610.7     .05       0  4871.6     .12       0
  5003.4     .07       0  5007.4     .12       0  5105.3     .05       0
  5138.6     .12       0  5339.9     .05       0
Bank Sta=5003.4,5007.4
XS Rating Curve= 0 ,0
Exp/Cntr=0.3,0.1

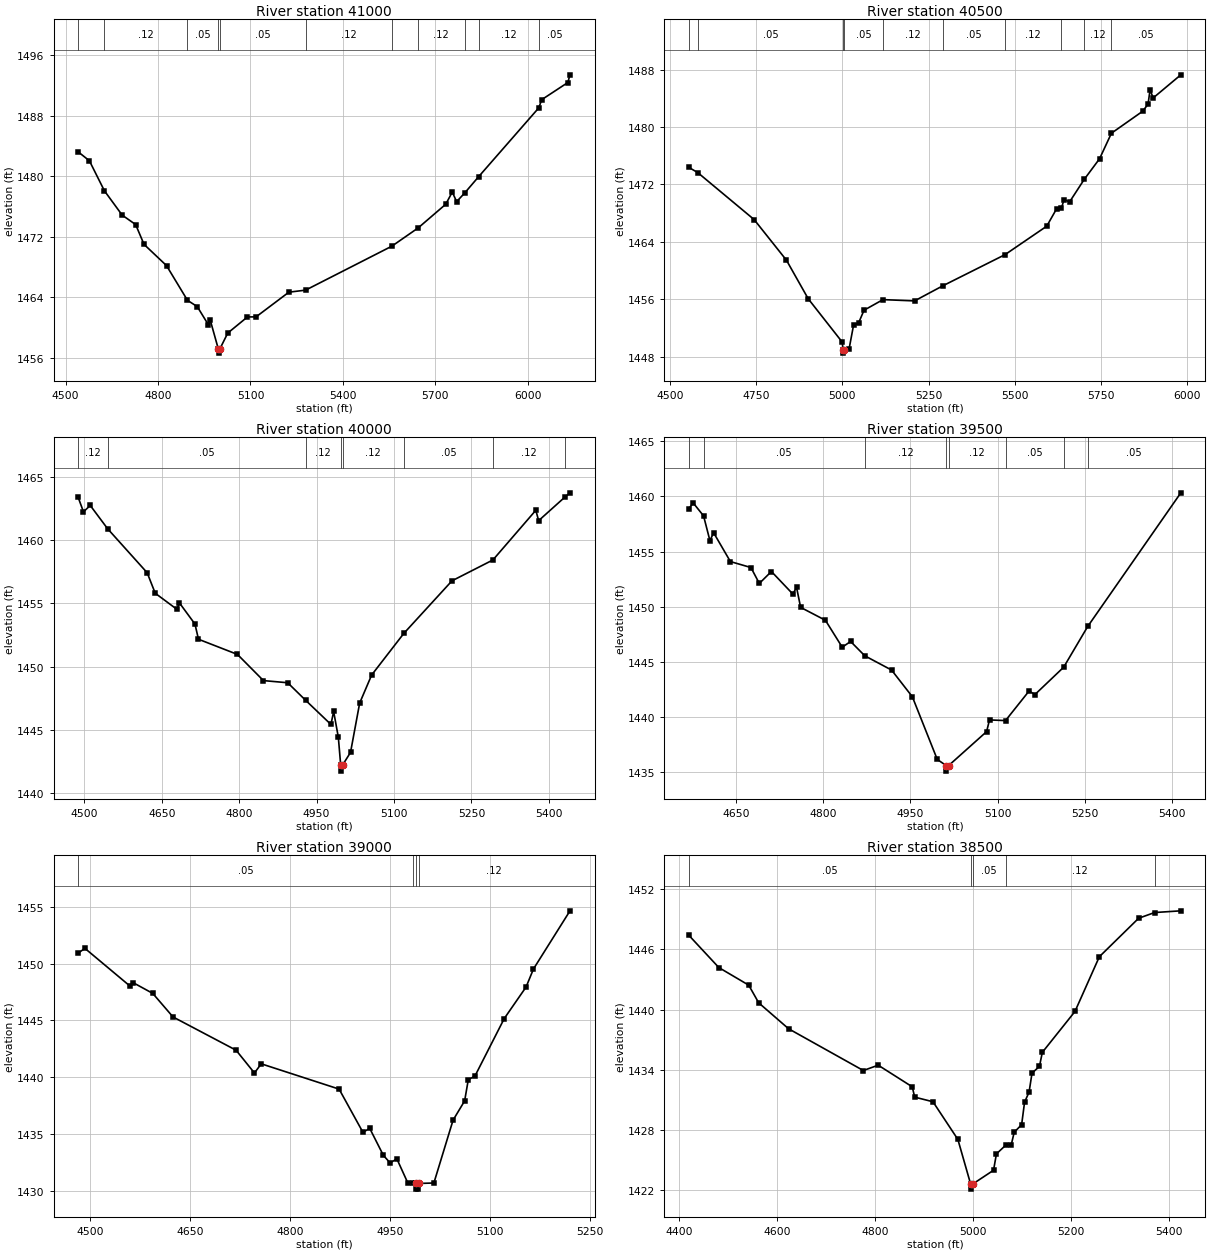
Type RM Length L Ch R = 1 ,41000   ,500,500,500
BEGIN DESCRIPTION:
LANG CREEK 80.0
END DESCRIPTION:
XS GIS Cut Line= 3
      2728755.65     10194553.14      2729124.01     10194278.62
       2729905.7     10193453.09
#Sta/Elev= 30
  4540.6 1483.24  4577.1 1482.06  4625.9 1478.09  4683.5 1474.88  4727.3 1473.63
  4754.4 1471.02  4827.4 1468.21  4895.4 1463.63  4927.3 1462.79  4962.9 1460.42
  4969.1 1461.05  4995.9 1457.15  4996.2 1456.65  4999.9 1457.15  5026.2  1459.3
  5090.1 1461.43  5118.1 1461.44  5224.5  1464.7  5278.8 1464.97  5558.9 1470.78
  5644.2 1473.19  5733.8 1476.32  5754.8 1477.93    5769 1476.66  5794.7 1477.78
  5840.7 1479.97  6035.9 1489.06  6044.8 1490.12  6129.8 1492.39  6136.9 1493.41
#Mann= 11 ,-1 , 0
  4540.6     .05       0  4625.9     .12       0  4895.4     .05       0
  4995.9     .05       0  4999.9     .05       0  5278.8     .12       0
  5558.9     .05       0  5644.2     .12       0  5794.7     .05       0
  5840.7     .12       0  6035.9     .05       0
Bank Sta=4995.9,4999.9
XS Rating Curve= 0 ,0
Exp/Cntr=0.3,0.1

Type RM Length L Ch R = 1 ,40500   ,500,500,500
BEGIN DESCRIPTION:
LANG CREEK 79.0
END DESCRIPTION:
XS GIS Cut Line= 3
      2729105.65     10194853.13       2729479.3     10194611.45
       2729955.7     10193753.09
#Sta/Elev= 30
    4555 1474.37  4580.7 1473.64    4744  1467.1  4837.7 1461.44    4901 1456.05
    5000 1449.99  5001.3 1448.98  5001.6 1448.48  5005.3 1448.98  5019.4 1449.05
  5032.4 1452.38  5046.8 1452.67  5062.8 1454.46  5117.8 1455.94  5209.3 1455.76
  5291.5 1457.87  5471.8 1462.21  5592.8 1466.18  5621.2 1468.59  5635.1 1468.65
    5643 1469.89    5659 1469.56  5701.3 1472.69    5746 1475.58  5780.4 1479.14
  5870.7 1482.19  5886.7 1483.19  5892.4 1485.18  5901.6 1484.06  5981.7 1487.28
#Mann= 10 ,-1 , 0
    4555     .12       0  4580.7     .05       0  5001.3     .05       0
  5005.3     .05       0  5117.8     .12       0  5291.5     .05       0
  5471.8     .12       0  5635.1     .05       0  5701.3     .12       0
  5780.4     .05       0
Bank Sta=5001.3,5005.3
XS Rating Curve= 0 ,0
Exp/Cntr=0.3,0.1

Type RM Length L Ch R = 1 ,40000   ,500,500,500
BEGIN DESCRIPTION:
LANG CREEK 78.0
END DESCRIPTION:
XS GIS Cut Line= 3
      2729355.72      10194953.1      2729853.38      10194833.2
       2730255.7      10194653.1
#Sta/Elev= 30
  4488.1 1463.39  4498.4 1462.24  4511.6 1462.74  4545.2  1460.9  4621.8 1457.42
  4637.4  1455.8  4679.3 1454.53  4684.4 1455.03  4714.4 1453.36  4721.2 1452.16
  4796.7 1450.96    4847 1448.89    4894 1448.72  4928.8 1447.33  4977.8 1445.42
    4983 1446.45  4992.1 1444.41  4996.6 1442.23  4996.9 1441.73  5000.6 1442.23
  5015.7 1443.21  5033.4 1447.11  5056.6 1449.33  5118.9 1452.62  5212.2 1456.78
  5291.5 1458.43  5374.6 1462.36  5380.1 1461.54  5430.3 1463.38  5440.8 1463.74
#Mann= 8 ,-1 , 0
  4488.1     .12       0  4545.2     .05       0  4928.8     .12       0
  4996.6     .07       0  5000.6     .12       0  5118.9     .05       0
  5291.5     .12       0  5430.3     .05       0
Bank Sta=4996.6,5000.6
XS Rating Curve= 0 ,0
Exp/Cntr=0.3,0.1

Type RM Length L Ch R = 1 ,39500   ,500,500,500
BEGIN DESCRIPTION:
LANG CREEK 77.0
END DESCRIPTION:
XS GIS Cut Line= 3
       2729755.7      10195503.1      2730092.27     10195234.36
      2730505.69     10195203.11
#Sta/Elev= 30
  4569.3 1458.89  4576.5 1459.41  4594.4 1458.23  4605.3 1455.99  4611.7  1456.7
  4640.5 1454.09  4675.8 1453.55  4690.2 1452.11    4711 1453.19  4747.8 1451.15
  4754.2 1451.75  4761.2 1449.94  4803.8 1448.77  4832.7 1446.33  4847.1 1446.85
  4871.5 1445.55  4917.5 1444.26  4953.2 1441.84    4996 1436.16  5011.5  1435.6
  5011.7  1435.1  5015.5  1435.6  5080.8 1438.68  5085.8 1439.74  5113.3 1439.68
  5153.8 1442.36  5163.9 1442.04  5213.3 1444.52  5254.6 1448.21  5414.6 1460.32
#Mann= 8 ,-1 , 0
  4569.3     .12       0  4594.4     .05       0  4871.5     .12       0
  5011.5     .07       0  5015.5     .12       0  5113.3     .05       0
  5213.3     .12       0  5254.6     .05       0
Bank Sta=5011.5,5015.5
XS Rating Curve= 0 ,0
Exp/Cntr=0.3,0.1

Type RM Length L Ch R = 1 ,39000   ,500,500,500
BEGIN DESCRIPTION:
LANG CREEK 76.0
END DESCRIPTION:
XS GIS Cut Line= 3
      2729955.68     10195653.11       2730464.6      10195553.9
      2730555.69     10195353.09
#Sta/Elev= 30
  4481.5 1450.94  4491.7 1451.36  4558.9 1448.06    4564 1448.34  4593.6 1447.39
  4624.1 1445.31  4718.8 1442.38  4746.4 1440.37  4756.6 1441.18  4873.6 1438.95
  4909.4 1435.14  4919.6 1435.49    4940 1433.12  4950.2 1432.44  4960.4  1432.8
  4976.8 1430.68  4985.3 1430.68  4988.9 1430.63  4989.2 1430.13  4992.7 1430.13
  4992.9 1430.63    5016 1430.67  5044.8 1436.21  5062.2 1437.91  5067.7 1439.78
  5077.7  1440.1  5121.7 1445.17  5154.5 1447.95  5165.6 1449.54  5220.5 1454.67
#Mann= 4 ,-1 , 0
  4481.5     .05       0  4985.3     .12       0  4988.9     .07       0
  4992.9     .12       0
Bank Sta=4988.9,4992.9
XS Rating Curve= 0 ,0
Exp/Cntr=0.3,0.1

Type RM Length L Ch R = 1 ,38500   ,500,500,500
BEGIN DESCRIPTION:
LANG CREEK 75.0
END DESCRIPTION:
XS GIS Cut Line= 3
      2730055.66     10195903.11      2730625.84     10196010.44
       2730855.7     10195653.08
#Sta/Elev= 30
  4419.8 1447.39  4480.9 1444.19  4541.9 1442.44  4562.3 1440.68  4623.3  1438.1
  4776.1 1433.94  4806.5 1434.47    4876 1432.32  4881.1 1431.29  4918.4 1430.83
  4969.3 1427.08  4995.4 1422.63  4995.6 1422.13  4999.4 1422.63  5042.2 1424.01
  5048.1 1425.64    5067  1426.5  5078.5 1426.57  5084.4 1427.79  5099.6 1428.55
  5105.6 1430.79  5114.8 1431.79  5120.8 1433.68    5136 1434.35  5141.9 1435.75
  5208.6 1439.82  5258.4 1445.27  5338.7  1449.1  5371.3 1449.67  5424.9 1449.84
#Mann= 5 ,-1 , 0
  4419.8     .05       0  4995.4     .05       0  4999.4     .05       0
    5067     .12       0  5371.3     .05       0
Bank Sta=4995.4,4999.4
XS Rating Curve= 0 ,0
Exp/Cntr=0.3,0.1

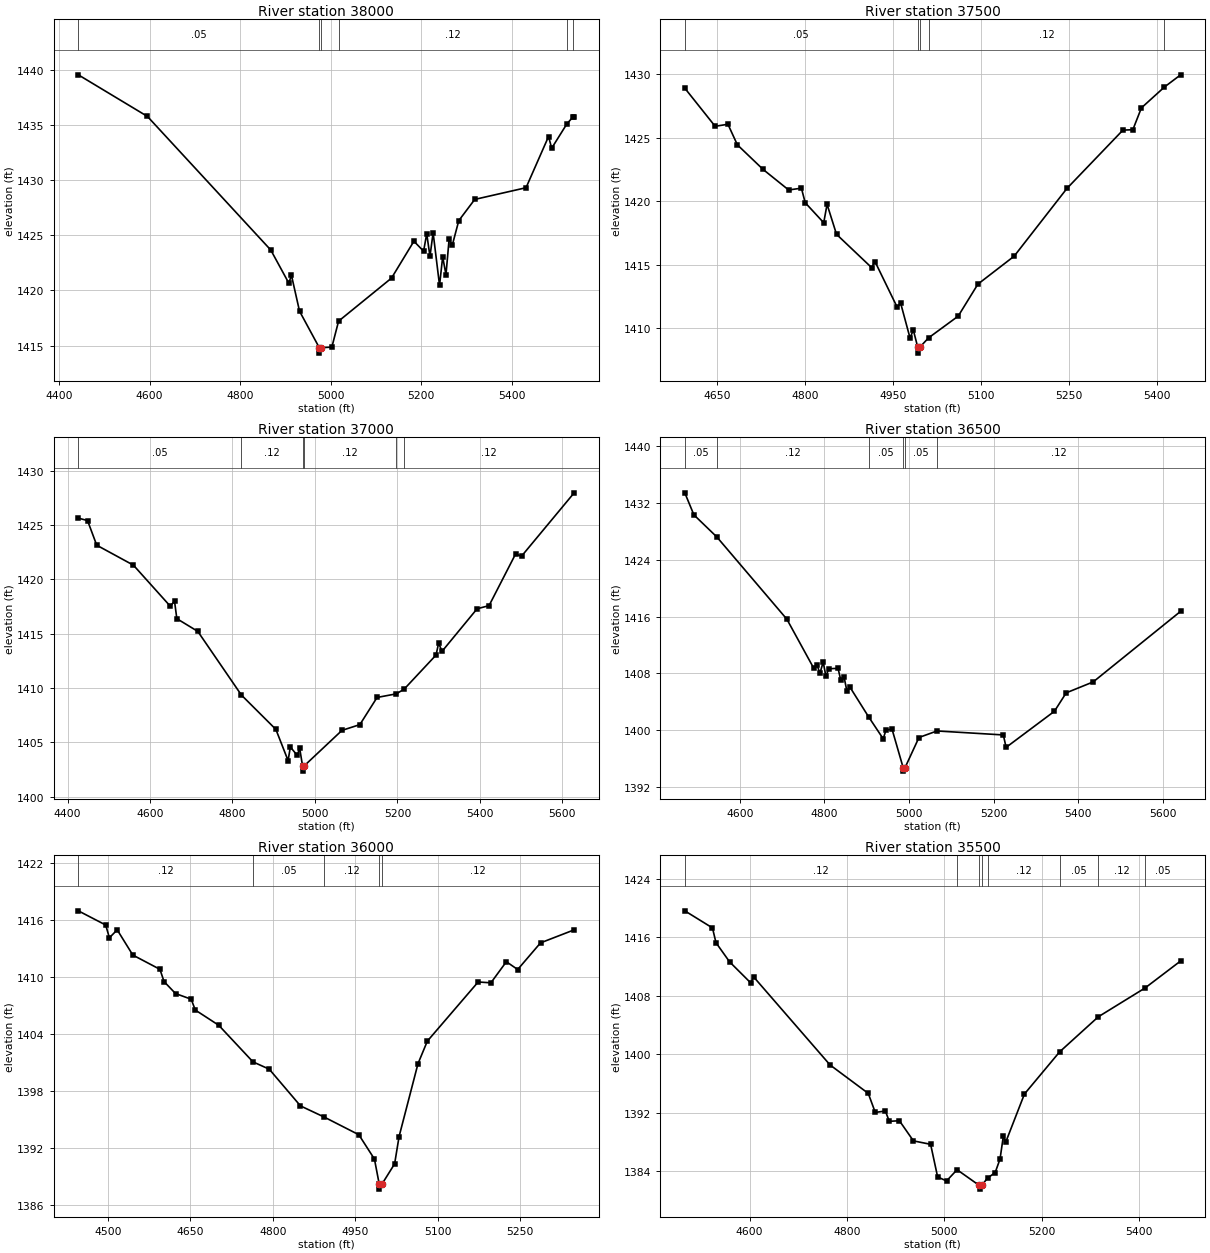
Type RM Length L Ch R = 1 ,38000   ,500,500,500
BEGIN DESCRIPTION:
LANG CREEK 74.0
END DESCRIPTION:
XS GIS Cut Line= 3
      2730155.72     10196253.13      2730667.15     10196474.03
      2731055.72     10196103.08
#Sta/Elev= 30
  4442.9 1439.54  4595.4 1435.77  4867.7 1423.66  4907.6 1420.65  4913.1  1421.4
  4931.1 1418.12  4974.6 1414.82  4974.9 1414.32  4978.6 1414.82  5002.4 1414.86
  5017.3 1417.22  5134.1 1421.12  5183.5 1424.46  5204.9 1423.56  5211.8 1425.14
    5219 1423.09  5225.9 1425.24  5240.1 1420.46    5247 1423.05  5254.3 1421.43
  5261.2 1424.63  5268.4 1424.13  5282.6 1426.33  5317.8 1428.25    5431 1429.31
  5480.7 1433.95  5487.6 1432.89  5521.2  1435.1    5534 1435.69  5537.2 1435.69
#Mann= 6 ,-1 , 0
  4442.9     .05       0  4974.6     .05       0  4978.6     .05       0
  5017.3     .12       0  5521.2     .05       0    5534     .12       0
Bank Sta=4974.6,4978.6
XS Rating Curve= 0 ,0
Exp/Cntr=0.3,0.1

Type RM Length L Ch R = 1 ,37500   ,500,500,500
BEGIN DESCRIPTION:
LANG CREEK 73.0
END DESCRIPTION:
XS GIS Cut Line= 3
       2730455.7     10196753.12      2730811.08     10196947.37
      2731205.66     10196753.13
#Sta/Elev= 30
    4595 1428.89  4646.7 1425.89  4668.5 1426.05  4684.6 1424.43  4728.3  1422.5
  4771.9 1420.88  4793.7 1421.02  4800.1 1419.88  4831.7  1418.3  4837.4 1419.75
  4853.5 1417.39  4913.3 1414.77    4919 1415.25  4956.9 1411.65  4962.6    1412
  4978.7 1409.24  4984.4 1409.85  4991.7 1408.54    4992 1408.04  4996.1 1408.54
  5010.3 1409.24  5060.8 1410.95  5094.4 1413.47  5156.2 1415.67  5246.1    1421
  5341.5 1425.59  5358.4 1425.62    5373 1427.34  5412.2 1428.98  5439.8 1429.94
#Mann= 5 ,-1 , 0
    4595     .05       0  4991.7     .05       0  4996.1     .05       0
  5010.3     .12       0  5412.2     .05       0
Bank Sta=4991.7,4996.1
XS Rating Curve= 0 ,0
Exp/Cntr=0.3,0.1

Type RM Length L Ch R = 1 ,37000   ,500,500,500
BEGIN DESCRIPTION:
LANG CREEK 72.0
END DESCRIPTION:
XS GIS Cut Line= 3
      2730355.65     10197653.13      2730870.66     10197400.12
      2731255.68     10196903.11
#Sta/Elev= 30
  4426.2 1425.64  4448.5 1425.42  4470.8 1423.15  4559.9 1421.31  4649.1 1417.54
  4659.5    1418  4665.1 1416.39  4715.9 1415.22  4821.7 1409.36  4905.3  1406.2
  4934.9 1403.33  4940.4 1404.58  4957.3  1403.8  4962.9 1404.49  4969.9 1402.86
  4970.2 1402.36  4974.4 1402.86  5065.6 1406.11    5109 1406.64  5150.7 1409.14
  5197.2 1409.47  5216.3  1409.9  5293.7 1413.04    5300 1414.14  5308.2 1413.38
  5393.3  1417.3  5422.3 1417.59  5486.6 1422.34  5501.1 1422.14  5628.7 1427.97
#Mann= 6 ,-1 , 0
  4426.2     .05       0  4821.7     .12       0  4969.9     .07       0
  4974.4     .12       0  5197.2     .05       0  5216.3     .12       0
Bank Sta=4969.9,4974.4
XS Rating Curve= 0 ,0
Exp/Cntr=0.3,0.1

Type RM Length L Ch R = 1 ,36500   ,500,500,500
BEGIN DESCRIPTION:
LANG CREEK 71.0
END DESCRIPTION:
XS GIS Cut Line= 3
      2730705.68     10198253.12      2731047.32     10197847.93
      2731455.71     10197353.08
#Sta/Elev= 30
    4470 1433.41  4491.5 1430.31  4545.7  1427.2  4711.2 1415.63    4775  1408.7
  4782.7 1409.16  4789.3 1408.01    4797 1409.61  4803.5 1407.59  4810.1 1408.66
  4832.1 1408.72  4838.7 1407.03  4846.4 1407.47    4853 1405.54  4860.7 1406.03
  4904.4 1401.89  4938.8 1398.81  4945.3 1400.02  4959.6 1400.18  4985.9 1394.76
  4986.2 1394.26  4990.5 1394.76  5023.3 1398.99  5065.9 1399.91  5222.7 1399.35
  5229.2  1397.6  5343.4 1402.68  5371.2 1405.27    5435 1406.81  5641.6 1416.74
#Mann= 6 ,-1 , 0
    4470     .05       0  4545.7     .12       0  4904.4     .05       0
  4985.9     .05       0  4990.5     .05       0  5065.9     .12       0
Bank Sta=4985.9,4990.5
XS Rating Curve= 0 ,0
Exp/Cntr=0.3,0.1

Type RM Length L Ch R = 1 ,36000   ,500,500,500
BEGIN DESCRIPTION:
LANG CREEK 70.0
END DESCRIPTION:
XS GIS Cut Line= 3
      2731105.65     10198203.15      2731476.51     10197791.86
      2731555.69     10197453.09
#Sta/Elev= 30
  4446.2 1416.98  4495.9 1415.49  4502.7 1414.15  4516.9 1414.98  4545.3 1412.33
  4594.6 1410.83  4602.1 1409.54    4623 1408.28  4651.4 1407.69  4658.9 1406.55
  4701.5 1404.95  4763.8  1401.1  4793.4 1400.33  4850.2 1396.47  4893.2  1395.3
  4956.3 1393.44  4984.7 1390.88  4993.5 1388.22  4993.8 1387.72  4998.1 1388.22
  5021.4 1390.38  5029.5 1393.25  5063.9 1400.91  5080.9 1403.28  5173.3  1409.5
  5196.5 1409.41  5224.6 1411.63  5245.2 1410.81  5286.7 1413.61  5347.9 1414.98
#Mann= 5 ,-1 , 0
  4446.2     .12       0  4763.8     .05       0  4893.2     .12       0
  4993.5     .07       0  4998.1     .12       0
Bank Sta=4993.5,4998.1
XS Rating Curve= 0 ,0
Exp/Cntr=0.3,0.1

Type RM Length L Ch R = 1 ,35500   ,500,500,500
BEGIN DESCRIPTION:
LANG CREEK 69.0
END DESCRIPTION:
XS GIS Cut Line= 3
      2731505.71     10198453.08      2731839.19     10198037.42
      2731805.68     10197553.08
#Sta/Elev= 30
  4467.1 1419.65  4523.9 1417.31  4531.2 1415.28  4559.1 1412.66  4602.3 1409.79
  4608.7 1410.58  4765.5 1398.53  4843.9 1394.64  4858.3 1392.03  4879.1 1392.22
  4887.1 1390.81  4907.9 1390.89  4936.7 1388.13    4972 1387.66  4986.4 1383.19
  5004.7 1382.64  5026.3 1384.18  5072.1 1382.02  5072.5 1381.52  5076.8 1382.02
  5088.9 1383.03  5104.6 1383.79  5114.6 1385.65  5121.4 1388.79  5126.4 1387.98
  5164.7 1394.55  5236.9 1400.32  5316.4 1405.13  5412.5 1409.08  5485.5 1412.78
#Mann= 8 ,-1 , 0
  4467.1     .12       0  5026.3     .05       0  5072.1     .07       0
  5076.8     .05       0  5088.9     .12       0  5236.9     .05       0
  5316.4     .12       0  5412.5     .05       0
Bank Sta=5072.1,5076.8
XS Rating Curve= 0 ,0
Exp/Cntr=0.3,0.1

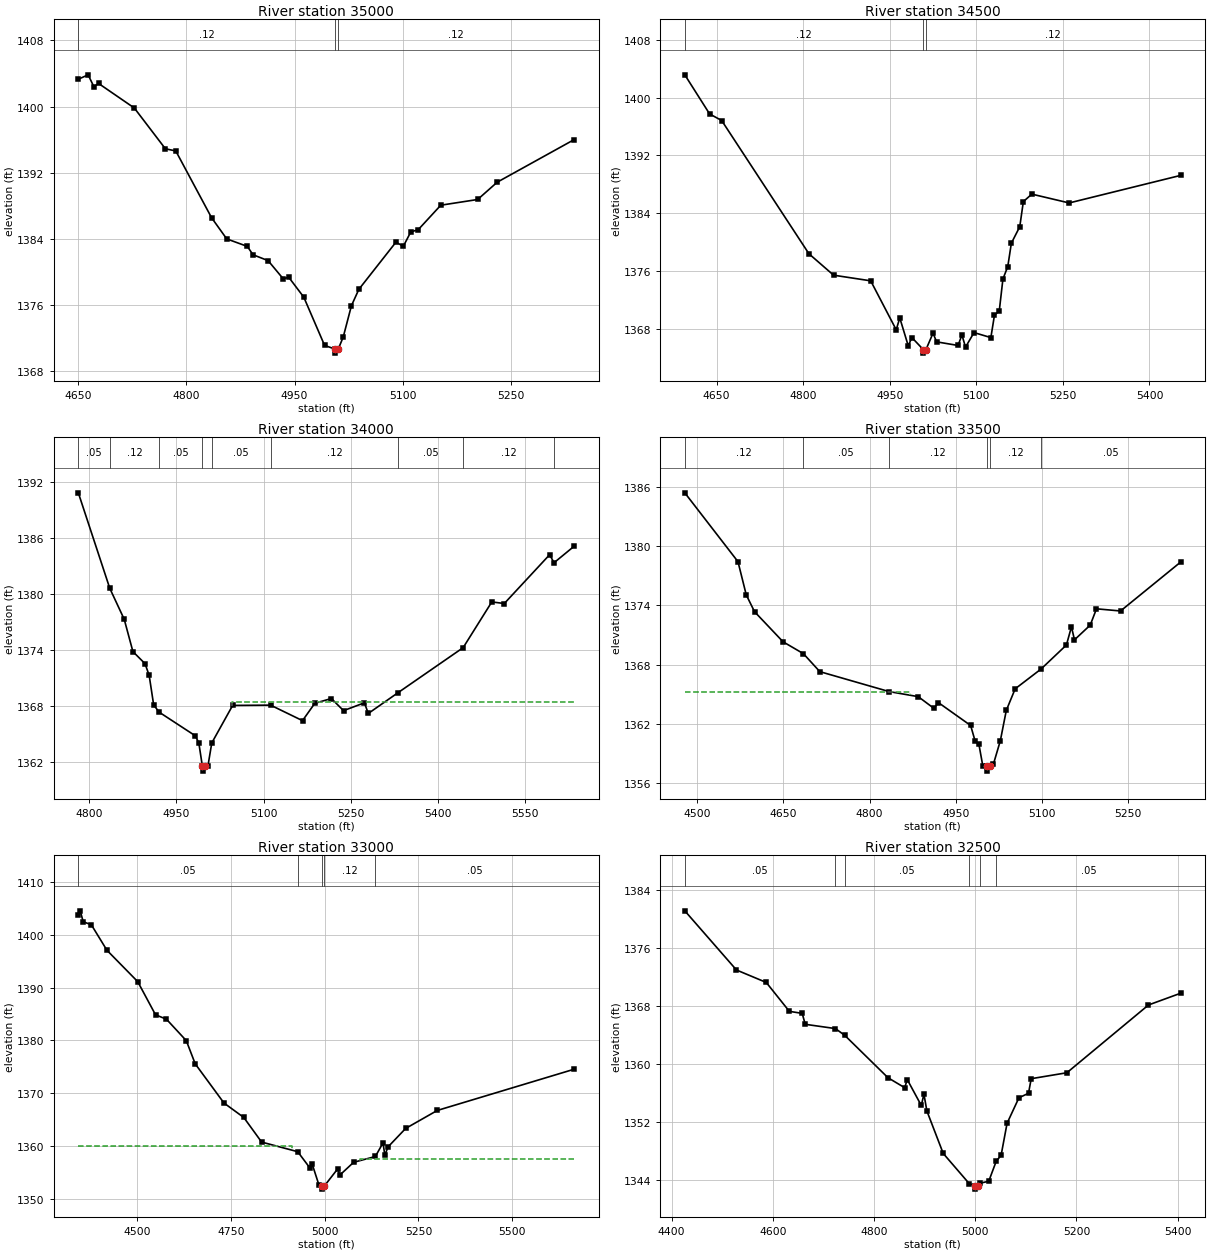
Type RM Length L Ch R = 1 ,35000   ,500,500,500
BEGIN DESCRIPTION:
LANG CREEK 68.0
END DESCRIPTION:
XS GIS Cut Line= 3
      2732055.68     10198453.12      2732275.54     10198181.05
      2732355.69      10197853.1
#Sta/Elev= 30
  4650.2 1403.32  4663.8 1403.85  4671.8  1402.4  4678.2 1402.81  4727.8 1399.84
  4770.9 1394.91  4785.3 1394.65  4834.9 1386.58  4855.9 1384.02  4884.5 1383.11
  4892.4  1382.1  4913.3 1381.39  4934.1 1379.21    4942 1379.37  4962.8 1376.97
  4991.6 1371.14  5005.8 1370.71  5006.1 1370.21  5010.6 1370.71  5017.5 1372.17
  5028.8 1375.94  5039.1 1377.92  5090.5 1383.62  5100.8 1383.13  5111.1 1384.86
  5121.4 1385.13  5152.7 1388.09  5203.8 1388.78  5230.9 1390.87  5337.6 1396.02
#Mann= 3 ,-1 , 0
  4650.2     .12       0  5005.8     .07       0  5010.6     .12       0
Bank Sta=5005.8,5010.6
XS Rating Curve= 0 ,0
Exp/Cntr=0.3,0.1

Type RM Length L Ch R = 1 ,34500   ,500,500,500
BEGIN DESCRIPTION:
LANG CREEK 67.0
END DESCRIPTION:
XS GIS Cut Line= 3
      2732205.72     10198703.09      2732535.65     10198468.03
       2732805.7     10198103.08
#Sta/Elev= 30
  4594.9 1403.15  4637.9 1397.74  4658.8 1396.83    4810  1378.4  4852.7 1375.44
    4917 1374.66  4961.2 1367.89  4967.4 1369.53  4982.1 1365.66  4988.3 1366.82
    5008 1365.16  5008.4 1364.66  5012.8 1365.16    5025 1367.42  5031.2 1366.22
  5068.3 1365.72  5075.1 1367.17  5081.3 1365.49    5096  1367.5  5125.2 1366.81
  5131.4 1369.89  5139.8 1370.52  5146.1 1374.91  5154.5 1376.63  5160.7 1379.86
  5175.3 1382.15  5181.5 1385.62  5196.2 1386.65  5260.9 1385.43    5454 1389.24
#Mann= 3 ,-1 , 0
  4594.9     .12       0    5008     .07       0  5012.8     .12       0
Bank Sta=5008,5012.8
XS Rating Curve= 0 ,0
Exp/Cntr=0.3,0.1

Type RM Length L Ch R = 1 ,34000   ,500,500,500
BEGIN DESCRIPTION:
LANG CREEK 66.0
END DESCRIPTION:
XS GIS Cut Line= 3
      2732555.65     10199003.13      2732735.03      10198878.2
      2733155.65     10198403.15
#Sta/Elev= 30
  4781.4 1390.79  4835.5 1380.56  4860.4 1377.23  4875.3 1373.78  4896.2 1372.48
  4903.3 1371.22    4911 1368.07  4920.4 1367.29  4982.6 1364.76  4988.7 1363.99
  4994.9 1361.47  4995.3 1360.97  4999.8 1361.47  5004.3 1361.49    5011 1363.99
  5046.9 1368.01  5112.2 1368.04  5167.1 1366.38  5188.3 1368.24  5216.8 1368.75
  5237.7 1367.45  5273.6 1368.29  5280.3 1367.15  5331.8 1369.39  5443.5  1374.2
  5492.8  1379.1  5514.3 1378.93  5592.3 1384.16  5599.9  1383.3  5634.5 1385.07
#Mann= 9 ,-1 , 0
  4781.4     .05       0  4835.5     .12       0  4920.4     .05       0
  4994.9     .07       0    5011     .05       0  5112.2     .12       0
  5331.8     .05       0  5443.5     .12       0  5599.9     .05       0
#XS Ineff= 2 , 0
                         5046.59         1368.33
Permanent Ineff=
       F       F
Bank Sta=4994.9,4999.8
XS Rating Curve= 0 ,0
Exp/Cntr=0.3,0.1

Type RM Length L Ch R = 1 ,33500   ,500,500,500
BEGIN DESCRIPTION:
LANG CREEK 65.0
END DESCRIPTION:
XS GIS Cut Line= 3
      2732647.35     10199255.14      2733054.99     10198929.56
      2733155.68     10198603.14
#Sta/Elev= 30
  4478.3  1385.4  4570.9 1378.43  4585.3 1375.07  4599.7 1373.37  4649.4 1370.32
  4684.8 1369.12  4713.4  1367.3  4834.1 1365.28  4884.7 1364.77  4911.9 1363.59
    4920 1364.16    4976 1361.85    4984 1360.23  4990.4 1359.94  4997.2 1357.75
  5004.2 1357.73  5004.5 1357.23  5009.3 1357.73  5015.7 1357.95  5027.7 1360.31
  5038.1 1363.38  5053.5 1365.56  5098.5 1367.56  5142.8    1370  5151.5 1371.84
  5156.8 1370.52  5184.2 1372.01  5195.1 1373.66    5237 1373.44  5341.6 1378.39
#Mann= 6 ,-1 , 0
  4478.3     .12       0  4684.8     .05       0  4834.1     .12       0
  5004.2     .07       0  5009.3     .12       0  5098.5     .05       0
#XS Ineff= 2 , 0
         4870.45 1365.25
Permanent Ineff=
       F       F
Bank Sta=5004.2,5009.3
XS Rating Curve= 0 ,0
Exp/Cntr=0.3,0.1

Type RM Length L Ch R = 1 ,33000   ,500,500,500
BEGIN DESCRIPTION:
LANG CREEK 64.0
END DESCRIPTION:
XS GIS Cut Line= 3
      2732443.65     10199469.02      2733049.69     10199214.53
      2733705.69     10199103.11
#Sta/Elev= 30
  4342.7 1403.69  4347.7 1404.55  4355.7 1402.48  4377.4 1401.91    4419 1397.08
  4501.1 1391.14  4548.6 1384.86  4577.8 1384.02  4630.7 1379.96  4654.5 1375.57
  4731.2 1368.15  4784.1 1365.41  4831.7 1360.75  4927.9 1358.93  4961.3 1355.77
  4966.7 1356.55  4984.8 1352.57  4992.7 1352.34  4993.1 1351.84    4998 1352.34
  5034.9 1355.71    5040 1354.48  5077.1 1356.92  5135.1 1358.02  5155.5 1360.61
  5160.5 1358.21  5168.4  1359.8  5215.8 1363.33  5300.2 1366.74  5665.4 1374.55
#Mann= 5 ,-1 , 0
  4342.7     .05       0  4927.9     .12       0  4992.7     .07       0
    4998     .12       0  5135.1     .05       0
#XS Ineff= 2 , 0
         4912.73    1360 5093.64         1357.64
Permanent Ineff=
       F       F
Bank Sta=4992.7,4998
XS Rating Curve= 0 ,0
Exp/Cntr=0.3,0.1

Type RM Length L Ch R = 1 ,32500   ,500,500,500
BEGIN DESCRIPTION:
LANG CREEK 63.0
END DESCRIPTION:
XS GIS Cut Line= 3
      2732677.96     10199815.31      2733227.18     10199648.46
      2733604.78     10199499.57
#Sta/Elev= 30
    4426 1381.19  4528.1 1373.02    4587  1371.3  4632.6 1367.31    4658 1367.03
    4664 1365.52  4723.7 1364.93  4742.2 1363.99  4827.6 1358.14  4860.5 1356.77
  4865.7 1357.88  4893.4 1354.31  4898.6 1355.88  4904.4 1353.56  4936.7 1347.69
    4988 1343.53  4999.7 1343.26  5000.1 1342.76    5005 1343.26  5009.1 1343.57
  5026.7 1343.85  5041.4  1346.6  5051.1 1347.43  5062.9 1351.85  5086.3 1355.37
  5105.3    1356  5110.6 1358.01  5181.1 1358.83  5342.4 1368.19  5405.9 1369.81
#Mann= 6 ,-1 , 0
    4426     .05       0  4723.7     .12       0  4742.2     .05       0
    4988     .07       0  5009.1     .05       0  5041.4     .05       0
Bank Sta=4999.7,5005
XS Rating Curve= 0 ,0
Exp/Cntr=0.3,0.1

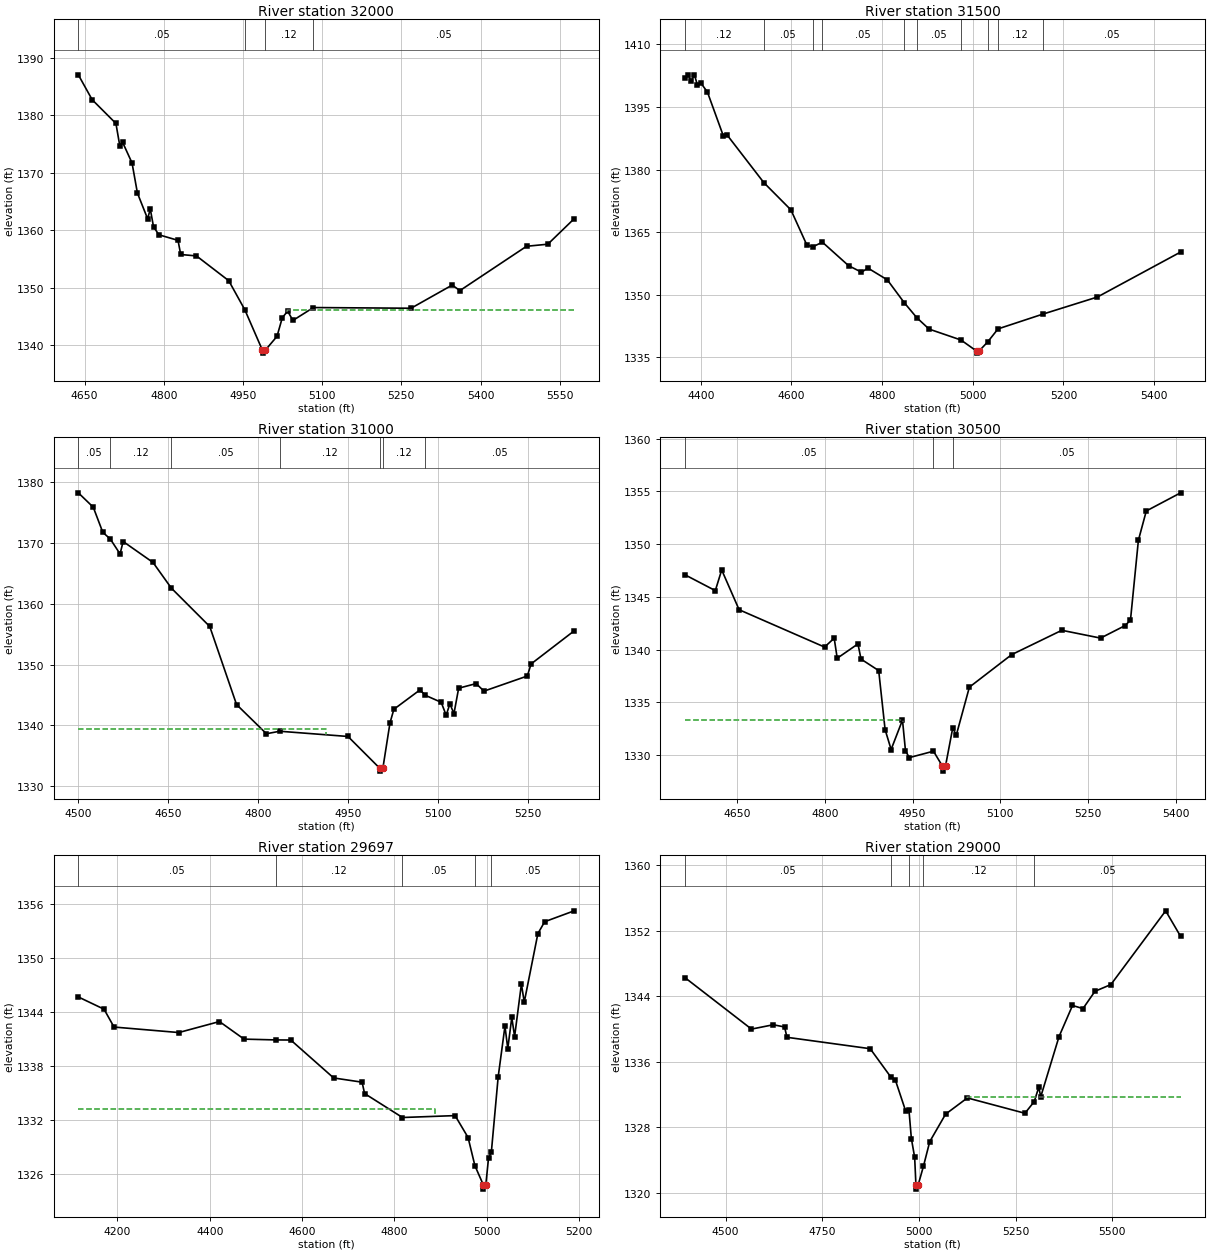
Type RM Length L Ch R = 1 ,32000   ,500,500,500
BEGIN DESCRIPTION:
LANG CREEK 62.0
END DESCRIPTION:
XS GIS Cut Line= 3
      2732705.72     10200003.12      2733061.28     10200069.98
      2733635.34     10200131.06
#Sta/Elev= 30
  4638.2 1387.02  4664.4 1382.69  4709.4 1378.56  4716.9 1374.58    4722 1375.29
  4739.9 1371.69  4750.1 1366.45  4769.4 1361.98  4774.5 1363.67  4780.6 1360.58
  4790.8 1359.19    4827 1358.22  4832.1 1355.76    4862 1355.51  4923.1  1351.2
  4953.6 1346.13  4986.9  1339.1  4987.3  1338.6  4992.2  1339.1  5014.5 1341.52
  5024.5 1344.76  5034.6  1345.9  5044.7 1344.29  5083.4 1346.53  5268.4 1346.41
  5346.3 1350.44  5360.9 1349.48  5487.1 1357.19  5527.4 1357.55  5577.3 1361.98
#Mann= 4 ,-1 , 0
  4638.2     .05       0  4953.6     .07       0  4992.2     .12       0
  5083.4     .05       0
#XS Ineff= 2 , 0
                         5034.09         1346.14
Permanent Ineff=
       F       F
Bank Sta=4986.9,4992.2
XS Rating Curve= 0 ,0
Exp/Cntr=0.3,0.1

Type RM Length L Ch R = 1 ,31500   ,500,500,500
BEGIN DESCRIPTION:
LANG CREEK 61.0
END DESCRIPTION:
XS GIS Cut Line= 3
      2732705.67     10200903.12       2733185.5     10200486.74
      2733605.72     10200303.09
#Sta/Elev= 30
  4364.7 1401.89  4371.8 1402.72  4378.5 1401.27  4386.1 1402.67  4392.7 1400.19
  4400.3 1400.73  4414.6 1398.59  4449.7 1388.08  4457.3  1388.4    4539 1376.88
  4598.8 1370.34  4633.9 1361.93  4646.9 1361.48  4668.3 1362.59    4726 1356.96
  4754.5  1355.4  4768.8 1356.38  4811.5 1353.56  4848.6 1348.12  4876.4  1344.5
  4903.7 1341.75  4973.9 1339.14  5008.4 1336.49  5008.8 1335.99  5013.9 1336.49
  5032.9 1338.67  5055.7  1341.8    5154 1345.32  5274.9 1349.44  5458.6 1360.23
#Mann= 10 ,-1 , 0
  4364.7     .12       0    4539     .05       0  4646.9     .12       0
  4668.3     .05       0  4848.6     .12       0  4876.4     .05       0
  4973.9     .07       0  5032.9     .05       0  5055.7     .12       0
    5154     .05       0
Bank Sta=5008.4,5013.9
XS Rating Curve= 0 ,0
Exp/Cntr=0.3,0.1

Type RM Length L Ch R = 1 ,31000   ,500,500,500
BEGIN DESCRIPTION:
LANG CREEK 60.0
END DESCRIPTION:
XS GIS Cut Line= 3
      2732955.71     10200953.11       2733444.2     10200850.27
       2733705.7      10200653.1
#Sta/Elev= 30
  4500.8 1378.29  4525.7 1375.92  4541.6 1371.78    4554 1370.69  4570.4 1368.22
  4575.5 1370.27  4625.3 1366.82  4655.9 1362.59  4719.9 1356.27  4764.6 1343.41
  4814.4  1338.6  4836.7 1339.01  4950.4 1338.15  5003.1 1332.94  5003.5 1332.44
  5008.6 1332.94  5020.4 1340.37  5026.9 1342.63  5070.4 1345.82  5079.4 1344.93
  5105.8 1343.78  5114.1 1341.65  5120.3 1343.52  5127.1 1341.92  5134.9  1346.1
    5164 1346.86  5177.2 1345.62  5249.4 1348.11  5255.7  1350.1  5327.5 1355.55
#Mann= 7 ,-1 , 0
  4500.8     .05       0    4554     .12       0  4655.9     .05       0
  4836.7     .12       0  5003.1     .07       0  5008.6     .12       0
  5079.4     .05       0
#XS Ineff= 2 , 0
       0  4914.2  1339.4               0
Permanent Ineff=
       F       F
Bank Sta=5003.1,5008.6
XS Rating Curve= 0 ,0
Exp/Cntr=0.3,0.1

Type RM Length L Ch R = 1 ,30500   ,803,803,803
BEGIN DESCRIPTION:
LANG CREEK 59.0
END DESCRIPTION:
XS GIS Cut Line= 3
      2733054.74     10201302.36      2733479.49     10201192.21
      2733705.68     10200853.12
#Sta/Elev= 30
  4561.2  1347.1  4613.3 1345.59  4624.2 1347.55  4653.9 1343.78  4799.8 1340.24
  4816.2 1341.08  4821.4 1339.18  4856.8 1340.54    4862  1339.1  4892.2 1338.01
  4903.1 1332.42  4913.4 1330.53  4932.8 1333.32  4937.9 1330.42  4944.4 1329.76
  4985.7 1330.37  5000.7 1328.98  5001.2 1328.48  5006.3 1328.98  5018.6 1332.58
  5024.6 1331.88    5047 1336.44  5119.1 1339.52  5204.8 1341.83  5270.9 1341.09
    5313 1342.28    5322  1342.8  5335.5 1350.36    5349 1353.14  5407.6 1354.86
#Mann= 3 ,-1 , 0
  4561.2     .05       0  4985.7     .07       0  5018.6     .05       0
#XS Ineff= 2 , 0
       0 4933.18 1333.32               0
Permanent Ineff=
       F       F
Bank Sta=5000.7,5006.3
XS Rating Curve= 0 ,0
Exp/Cntr=0.3,0.1

Type RM Length L Ch R = 1 ,29697   ,697,697,697
BEGIN DESCRIPTION:
LANG CREEK 58.0
END DESCRIPTION:
XS GIS Cut Line= 3
      2733024.21     10201353.28      2733716.81     10201638.46
      2733905.66     10201903.07
#Sta/Elev= 30
  4115.2 1345.67  4170.9 1344.31  4192.5 1342.33  4332.8 1341.72  4420.9 1342.94
  4474.2 1340.99  4543.9  1340.9  4575.4 1340.89  4668.3 1336.68  4729.9 1336.21
  4735.3 1334.95  4817.4 1332.29  4931.4  1332.5  4959.5 1330.07  4974.3 1326.94
  4992.3 1324.84  4992.8 1324.34    4998 1324.84  5003.8 1327.79  5009.9 1328.44
  5024.7  1336.8  5039.4 1342.43  5045.5 1339.94  5054.2 1343.39  5060.3 1341.28
    5075 1347.09  5081.2  1345.1  5110.7  1352.7  5125.4 1354.02  5189.3 1355.23
#Mann= 5 ,-1 , 0
  4115.2     .05       0  4543.9     .12       0  4817.4     .05       0
  4974.3     .07       0  5009.9     .05       0
#XS Ineff= 2 , 0
         4888.41 1333.19
Permanent Ineff=
       F       F
Bank Sta=4992.3,4998
XS Rating Curve= 0 ,0
Exp/Cntr=0.3,0.1

Type RM Length L Ch R = 1 ,29000   ,500,500,500
BEGIN DESCRIPTION:
LANG CREEK 57.0
END DESCRIPTION:
XS GIS Cut Line= 3
      2732905.66     10201453.07       2733264.1     10201941.08
      2733920.56     10202106.99
#Sta/Elev= 30
  4394.5 1346.28    4567 1339.99  4623.3 1340.52  4652.6 1340.25  4658.8 1338.99
  4874.1  1337.6  4927.4 1334.15  4938.9 1333.82    4966 1329.98  4974.4 1330.09
  4980.6 1326.64  4989.1 1324.36  4992.4 1320.98  4992.9 1320.48  4998.1 1320.98
  5011.9 1323.28  5028.1 1326.27  5069.1 1329.62  5125.4  1331.6  5274.3 1329.73
  5298.4 1331.15  5310.1  1332.9  5315.3 1331.75  5362.6 1339.08  5397.4 1342.87
  5424.5 1342.49  5455.5  1344.6  5496.7 1345.42  5638.4 1354.41  5677.1 1351.29
#Mann= 5 ,-1 , 0
  4394.5     .05       0  4927.4     .12       0  4974.4     .07       0
  5011.9     .12       0  5298.4     .05       0
#XS Ineff= 2 , 0
                         5125.45         1331.75
Permanent Ineff=
       F       F
Bank Sta=4992.4,4998.1
XS Rating Curve= 0 ,0
Exp/Cntr=0.3,0.1