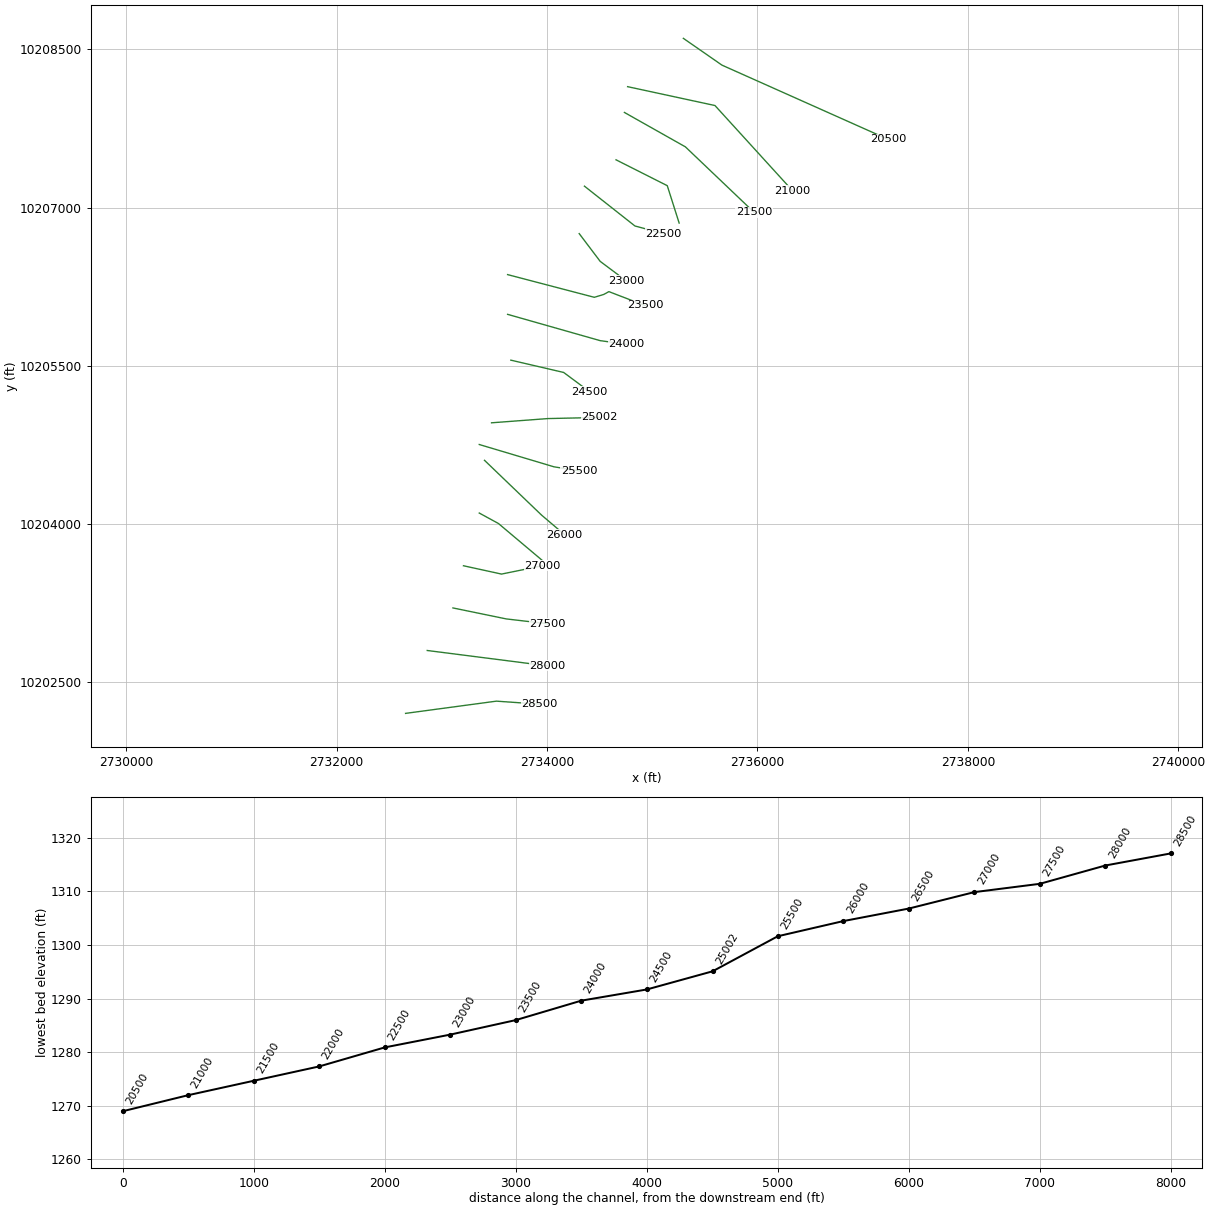
HEC-RAS study LANG CREEK.prj: LANG CREEK Base Level Engineering

--- LANG CREEK.g01 (geometry) --- (continued)

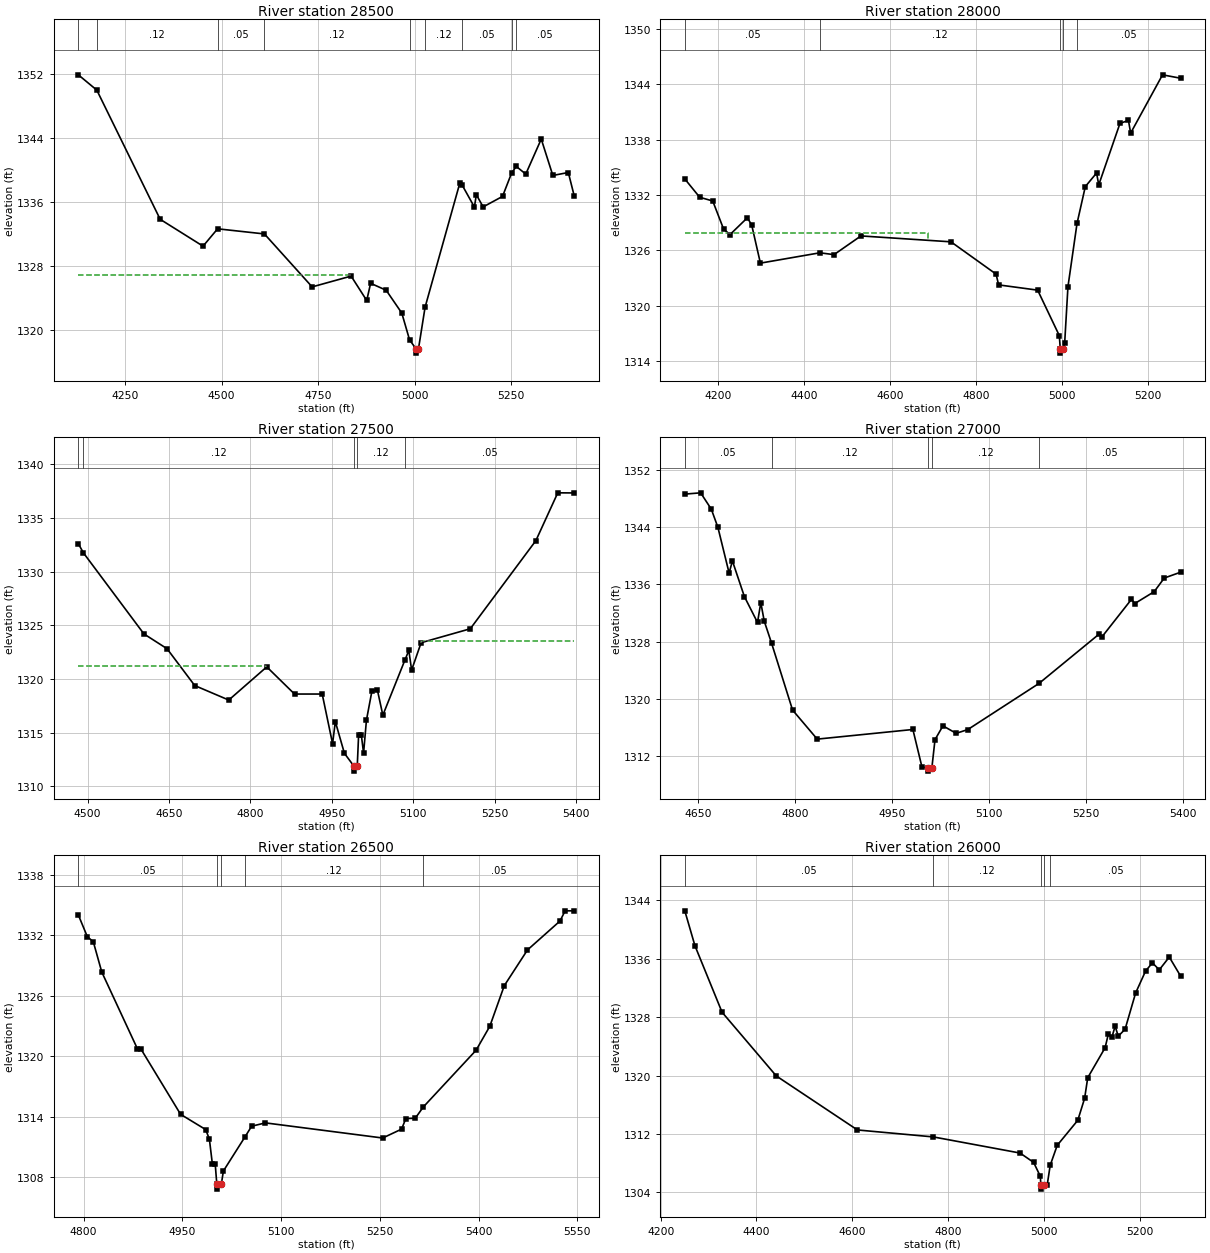
Type RM Length L Ch R = 1 ,28500   ,500,500,500
BEGIN DESCRIPTION:
LANG CREEK 56.0
END DESCRIPTION:
XS GIS Cut Line= 3
      2732655.67     10202203.11      2733518.72     10202319.04
      2733930.72     10202290.32
#Sta/Elev= 30
  4129.2 1351.89    4177 1349.98  4341.1 1333.83  4452.1 1330.47  4489.8 1332.64
    4611    1332  4734.6 1325.38  4835.5 1326.73  4875.9 1323.68    4886 1325.83
  4926.3 1324.96  4966.7 1322.11  4986.8 1318.76  5004.1  1317.6  5004.6  1317.1
  5009.8  1317.6    5027 1322.84  5117.3 1338.42  5122.5 1338.15  5154.7 1335.36
  5159.7  1336.9  5177.4 1335.38  5227.5 1336.69  5251.2 1339.63  5263.2 1340.44
  5287.7 1339.48  5327.8 1343.86  5357.8 1339.31  5397.9 1339.68    5413 1336.78
#Mann= 9 ,-1 , 0
  4129.2     .05       0    4177     .12       0  4489.8     .05       0
    4611     .12       0  4986.8     .07       0    5027     .12       0
  5122.5     .05       0  5251.2     .12       0  5263.2     .05       0
#XS Ineff= 2 , 0
         4834.55 1326.86
Permanent Ineff=
       F       F
Bank Sta=5004.1,5009.8
XS Rating Curve= 0 ,0
Exp/Cntr=0.3,0.1

Type RM Length L Ch R = 1 ,28000   ,500,500,500
BEGIN DESCRIPTION:
LANG CREEK 55.0
END DESCRIPTION:
XS GIS Cut Line= 3
      2732861.22     10202799.58      2733731.78     10202688.61
      2734005.69     10202653.11
#Sta/Elev= 30
  4122.4 1333.73  4157.1 1331.74  4187.4 1331.34  4212.8 1328.28  4227.7  1327.7
    4268 1329.52  4278.1 1328.73  4298.3  1324.6  4436.7 1325.72  4469.6 1325.52
  4532.3 1327.55  4741.8 1326.91  4846.7 1323.41  4852.7 1322.24  4943.5 1321.67
  4993.9 1316.74  4996.1 1315.34  4996.6 1314.84  5002.8 1315.34  5006.4 1315.95
    5014 1322.04  5035.1  1328.9  5054.4  1332.9  5080.6 1334.37  5085.7 1333.09
    5135 1339.75  5154.8 1340.08  5159.9  1338.7  5234.1 1345.02  5276.2 1344.65
#Mann= 5 ,-1 , 0
  4122.4     .05       0  4436.7     .12       0  4996.1     .07       0
  5002.8     .12       0  5035.1     .05       0
#XS Ineff= 2 , 0
         4687.27  1327.9
Permanent Ineff=
       F       F
Bank Sta=4996.1,5002.8
XS Rating Curve= 0 ,0
Exp/Cntr=0.3,0.1

Type RM Length L Ch R = 1 ,27500   ,500,500,500
BEGIN DESCRIPTION:
LANG CREEK 54.0
END DESCRIPTION:
XS GIS Cut Line= 3
      2733105.65     10203203.12      2733612.17     10203099.05
       2734005.7     10203053.11
#Sta/Elev= 30
  4482.9  1332.6  4492.4 1331.74  4603.7  1324.2  4646.3 1322.82  4697.3 1319.39
    4760 1318.04    4830 1321.13  4881.1  1318.6  4932.1  1318.6  4951.2 1313.98
  4956.3 1316.03    4973 1313.08    4990 1311.92  4990.5 1311.42  4996.7 1311.92
  4999.2 1314.81  5004.1 1314.81  5008.3  1313.1  5013.6 1316.17  5023.7 1318.88
  5033.7 1318.99  5043.8 1316.63  5084.5 1321.77  5091.7 1322.66  5096.8 1320.83
  5114.3 1323.38  5204.9 1324.68  5325.7 1332.89    5366 1337.34  5396.2 1337.33
#Mann= 5 ,-1 , 0
  4482.9     .05       0  4492.4     .12       0    4990     .07       0
  4996.7     .12       0  5084.5     .05       0
#XS Ineff= 2 , 0
         4828.98 1321.25  5114.2         1323.57
Permanent Ineff=
       F       F
Bank Sta=4990,4996.7
XS Rating Curve= 0 ,0
Exp/Cntr=0.3,0.1

Type RM Length L Ch R = 1 ,27000   ,500,500,500
BEGIN DESCRIPTION:
LANG CREEK 53.0
END DESCRIPTION:
XS GIS Cut Line= 3
      2733205.66     10203603.12      2733567.46     10203524.21
      2733955.72     10203603.12
#Sta/Elev= 30
  4629.7 1348.65  4654.2 1348.83  4670.7 1346.54  4680.9 1343.99  4698.2  1337.6
  4703.3  1339.3  4721.8 1334.31  4742.1 1330.68  4747.2 1333.46  4752.5 1330.87
  4763.9 1327.77  4796.3 1318.42  4834.4 1314.35  4982.3  1315.7  4996.5 1310.38
    5005 1310.37  5005.5 1309.87  5011.7 1310.37  5016.5 1314.28  5028.8 1316.21
  5049.2 1315.16  5067.2 1315.69  5177.3 1322.15  5269.6 1329.01  5274.7 1328.68
  5320.2 1333.92  5325.3 1333.33  5355.3 1334.99  5370.9  1336.9  5396.2 1337.72
#Mann= 5 ,-1 , 0
  4629.7     .05       0  4763.9     .12       0    5005     .07       0
  5011.7     .12       0  5177.3     .05       0
Bank Sta=5005,5011.7
XS Rating Curve= 0 ,0
Exp/Cntr=0.3,0.1

Type RM Length L Ch R = 1 ,26500   ,500,500,500
BEGIN DESCRIPTION:
LANG CREEK 52.0
END DESCRIPTION:
XS GIS Cut Line= 3
      2733355.71      10204103.1      2733538.32     10204003.72
       2733955.7      10203653.1
#Sta/Elev= 30
  4792.1 1333.99  4805.8 1331.83  4814.8 1331.34  4827.7 1328.33  4881.8 1320.72
  4887.5 1320.66  4947.4 1314.22  4985.4 1312.71  4991.1 1311.77  4995.7 1309.27
    5000 1309.27  5002.4  1307.3  5002.9  1306.8  5009.3  1307.3  5012.4  1308.6
  5044.9 1311.95  5055.3 1313.04  5076.2 1313.37  5254.3 1311.87    5283 1312.75
  5289.5  1313.8  5303.8 1313.83  5315.9 1314.94  5396.1 1320.57    5417 1322.95
    5439 1326.98  5474.2 1330.52  5523.6 1333.39  5531.4  1334.4  5545.1  1334.4
#Mann= 5 ,-1 , 0
  4792.1     .05       0  5002.4     .05       0  5009.3     .05       0
  5044.9     .12       0  5315.9     .05       0
Bank Sta=5002.4,5009.3
XS Rating Curve= 0 ,0
Exp/Cntr=0.3,0.1

Type RM Length L Ch R = 1 ,26000   ,500,500,500
BEGIN DESCRIPTION:
LANG CREEK 51.0
END DESCRIPTION:
XS GIS Cut Line= 3
      2733405.71     10204603.09      2733947.01     10204084.39
      2734164.99     10203899.55
#Sta/Elev= 30
  4250.3 1342.56  4271.5 1337.78  4328.1 1328.68  4441.3 1319.96  4610.8 1312.56
  4769.1 1311.61  4950.5  1309.4  4978.8 1308.12  4992.9  1306.2  4993.8 1304.96
  4994.3 1304.46  5000.8 1304.96  5007.3 1305.09  5013.4 1307.72  5028.1 1310.46
    5071 1313.88  5085.3 1316.89  5091.8 1319.71  5128.1 1323.82  5134.7 1325.66
  5142.4 1325.29    5149 1326.76  5155.6  1325.4  5169.8 1326.35  5191.8 1331.31
  5212.7 1334.33  5226.9 1335.44  5241.2 1334.48  5262.1 1336.23  5285.8 1333.62
#Mann= 5 ,-1 , 0
  4250.3     .05       0  4769.1     .12       0  4993.8     .07       0
  5000.8     .12       0  5013.4     .05       0
Bank Sta=4993.8,5000.8
XS Rating Curve= 0 ,0
Exp/Cntr=0.3,0.1

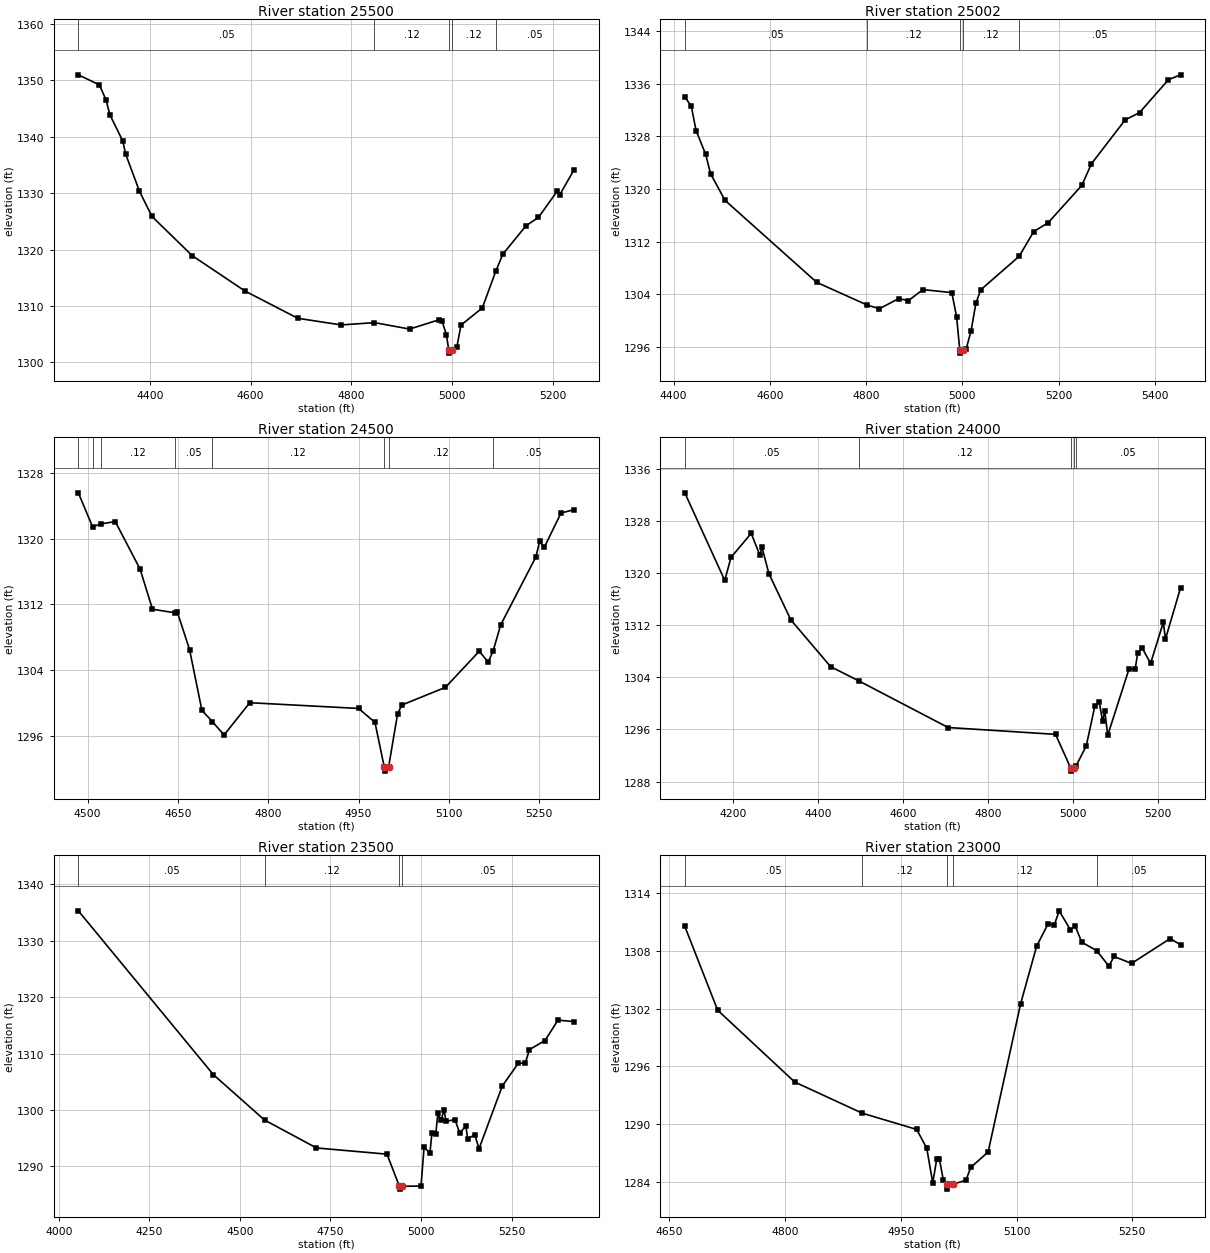
Type RM Length L Ch R = 1 ,25500   ,498,498,498
BEGIN DESCRIPTION:
LANG CREEK 50.0
END DESCRIPTION:
XS GIS Cut Line= 3
      2733355.66     10204753.12       2734066.5     10204541.39
      2734305.65     10204503.12
#Sta/Elev= 30
  4258.3    1351  4300.1 1349.22  4313.3 1346.54  4320.9 1343.91  4346.5 1339.26
  4352.2 1336.94  4379.6 1330.35  4404.4 1325.88  4484.3 1318.92  4589.1 1312.64
  4693.8 1307.81    4780 1306.63  4845.9 1307.04  4915.7  1305.9  4974.8 1307.57
    4980 1307.31  4988.7 1304.92  4993.4 1302.13  4993.9 1301.63  5000.5 1302.13
  5009.3 1302.63  5017.6  1306.6  5059.9 1309.64  5086.5 1316.12  5100.5 1319.16
  5146.7 1324.23  5171.3  1325.7  5208.7 1330.37  5213.8 1329.75  5242.2  1334.2
#Mann= 5 ,-1 , 0
  4258.3     .05       0  4845.9     .12       0  4993.4     .07       0
  5000.5     .12       0  5086.5     .05       0
Bank Sta=4993.4,5000.5
XS Rating Curve= 0 ,0
Exp/Cntr=0.3,0.1

Type RM Length L Ch R = 1 ,25002   ,502,502,502
BEGIN DESCRIPTION:
LANG CREEK 49.0
END DESCRIPTION:
XS GIS Cut Line= 3
      2733472.35     10204958.83      2734009.37     10204999.07
      2734500.93     10205009.76
#Sta/Elev= 30
  4423.4 1333.97  4436.8 1332.62  4446.8 1328.89  4466.9 1325.25  4476.9 1322.33
    4507 1318.28  4697.5 1305.83    4803 1302.36  4827.9 1301.83    4868 1303.37
    4888 1303.05  4918.1 1304.73  4978.2 1304.27  4988.2 1300.56  4994.7 1295.58
  4995.2 1295.08  5001.8 1295.58  5008.3 1295.77  5018.3 1298.51  5028.3 1302.68
  5038.3  1304.7  5118.2 1309.79  5148.3 1313.54  5178.3 1314.88  5248.3 1320.56
  5268.3 1323.84  5338.3  1330.5  5368.3 1331.62  5428.4 1336.62  5453.6 1337.35
#Mann= 5 ,-1 , 0
  4423.4     .05       0    4803     .12       0  4994.7     .07       0
  5001.8     .12       0  5118.2     .05       0
Bank Sta=4994.7,5001.8
XS Rating Curve= 0 ,0
Exp/Cntr=0.3,0.1

Type RM Length L Ch R = 1 ,24500   ,500,500,500
BEGIN DESCRIPTION:
LANG CREEK 48.0
END DESCRIPTION:
XS GIS Cut Line= 3
       2733655.7     10205553.11      2734157.84     10205436.48
      2734405.68     10205253.12
#Sta/Elev= 30
  4484.5 1325.57  4508.2 1321.43  4521.5 1321.78  4545.9 1322.07  4587.1 1316.28
  4607.7  1311.4  4644.4 1310.97  4648.7 1311.11  4669.3 1306.49  4689.8 1299.09
    4707 1297.73  4726.7 1296.09  4769.3 1300.02  4950.1 1299.32  4977.3 1297.63
  4992.8 1292.19  4993.3 1291.69    5000 1292.19    5015  1298.7  5022.2 1299.74
  5094.4 1301.89  5150.7 1306.29  5165.3 1304.95  5173.5 1306.27  5186.2 1309.49
  5244.7 1317.76  5250.9 1319.65  5258.6 1318.92  5286.4 1323.11  5308.3 1323.52
#Mann= 8 ,-1 , 0
  4484.5     .12       0  4508.2     .05       0  4521.5     .12       0
  4644.4     .05       0    4707     .12       0  4992.8     .07       0
    5000     .12       0  5173.5     .05       0
Bank Sta=4992.8,5000
XS Rating Curve= 0 ,0
Exp/Cntr=0.3,0.1

Type RM Length L Ch R = 1 ,24000   ,500,500,500
BEGIN DESCRIPTION:
LANG CREEK 47.0
END DESCRIPTION:
XS GIS Cut Line= 3
      2733625.18     10205987.53      2734504.82     10205738.15
      2734755.68     10205703.11
#Sta/Elev= 30
  4085.7 1332.29  4179.8 1318.85  4194.5 1322.39  4242.1 1326.07  4262.3 1322.76
  4267.5 1323.92  4283.7  1319.9  4335.3 1312.81  4429.2 1305.62  4496.5 1303.41
  4705.8 1296.29  4958.8 1295.24  4994.2  1290.1  4994.7  1289.6  5001.5  1290.1
  5006.6 1290.34  5031.2 1293.49  5051.4 1299.62  5061.5 1300.26  5069.6 1297.22
  5074.6 1298.87  5081.7 1295.11  5132.1 1305.33  5146.1 1305.19  5152.3 1307.74
  5162.4 1308.52  5182.6 1306.13  5212.5 1312.41  5217.6 1309.86  5253.3 1317.76
#Mann= 5 ,-1 , 0
  4085.7     .05       0  4496.5     .12       0  4994.2     .07       0
  5001.5     .12       0  5006.6     .05       0
Bank Sta=4994.2,5001.5
XS Rating Curve= 0 ,0
Exp/Cntr=0.3,0.1

Type RM Length L Ch R = 1 ,23500   ,500,500,500
BEGIN DESCRIPTION:
LANG CREEK 46.0
END DESCRIPTION:
XS GIS Cut Line= 5
      2733625.17     10206364.38      2734449.32     10206149.08
      2734539.29     10206176.28      2734587.94     10206202.85
      2734930.79     10206071.45
#Sta/Elev= 30
  4054.2 1335.31  4426.8 1306.27  4568.1 1298.22  4711.5 1293.27    4906 1292.17
  4940.3 1286.47  4940.8 1285.97  4947.6 1286.47    5000 1286.52  5008.4 1293.43
  5024.5 1292.33  5030.2 1295.99  5040.7 1295.76  5046.4 1299.38  5055.4 1298.18
  5063.5 1300.06  5068.9 1297.97  5093.6 1298.31  5106.6 1295.95  5123.6 1297.12
  5128.9 1294.89  5148.3 1295.62  5160.1 1293.14  5224.4 1304.28  5268.4 1308.27
  5287.7 1308.32  5299.3 1310.71  5342.2 1312.32  5377.8 1315.92  5422.6 1315.68
#Mann= 4 ,-1 , 0
  4054.2     .05       0  4568.1     .12       0  4940.3     .05       0
  4947.6     .05       0
Bank Sta=4940.3,4947.6
XS Rating Curve= 0 ,0
Exp/Cntr=0.3,0.1

Type RM Length L Ch R = 1 ,23000   ,500,500,500
BEGIN DESCRIPTION:
LANG CREEK 45.0
END DESCRIPTION:
XS GIS Cut Line= 3
      2734305.71     10206753.08      2734505.09       10206490.
      2734755.67     10206303.12
#Sta/Elev= 30
  4669.9 1310.55  4712.5 1301.84  4812.4 1294.38  4899.8 1291.15  4970.4 1289.46
  4983.5 1287.52  4991.3 1283.91  4996.4 1286.35    5000 1286.35  5005.1 1284.16
  5009.5 1283.76    5010 1283.26  5016.9 1283.76  5034.3 1284.18  5040.5 1285.51
  5063.1 1287.12  5105.2 1302.51    5126  1308.5  5140.6 1310.78    5149 1310.73
  5155.2 1312.16  5169.8 1310.18    5176 1310.57  5184.4  1308.9  5203.6 1308.04
  5219.8  1306.4  5226.1 1307.42    5249  1306.7  5299.1 1309.28  5312.6 1308.63
#Mann= 5 ,-1 , 0
  4669.9     .05       0  4899.8     .12       0  5009.5     .07       0
  5016.9     .12       0  5203.6     .05       0
Bank Sta=5009.5,5016.9
XS Rating Curve= 0 ,0
Exp/Cntr=0.3,0.1

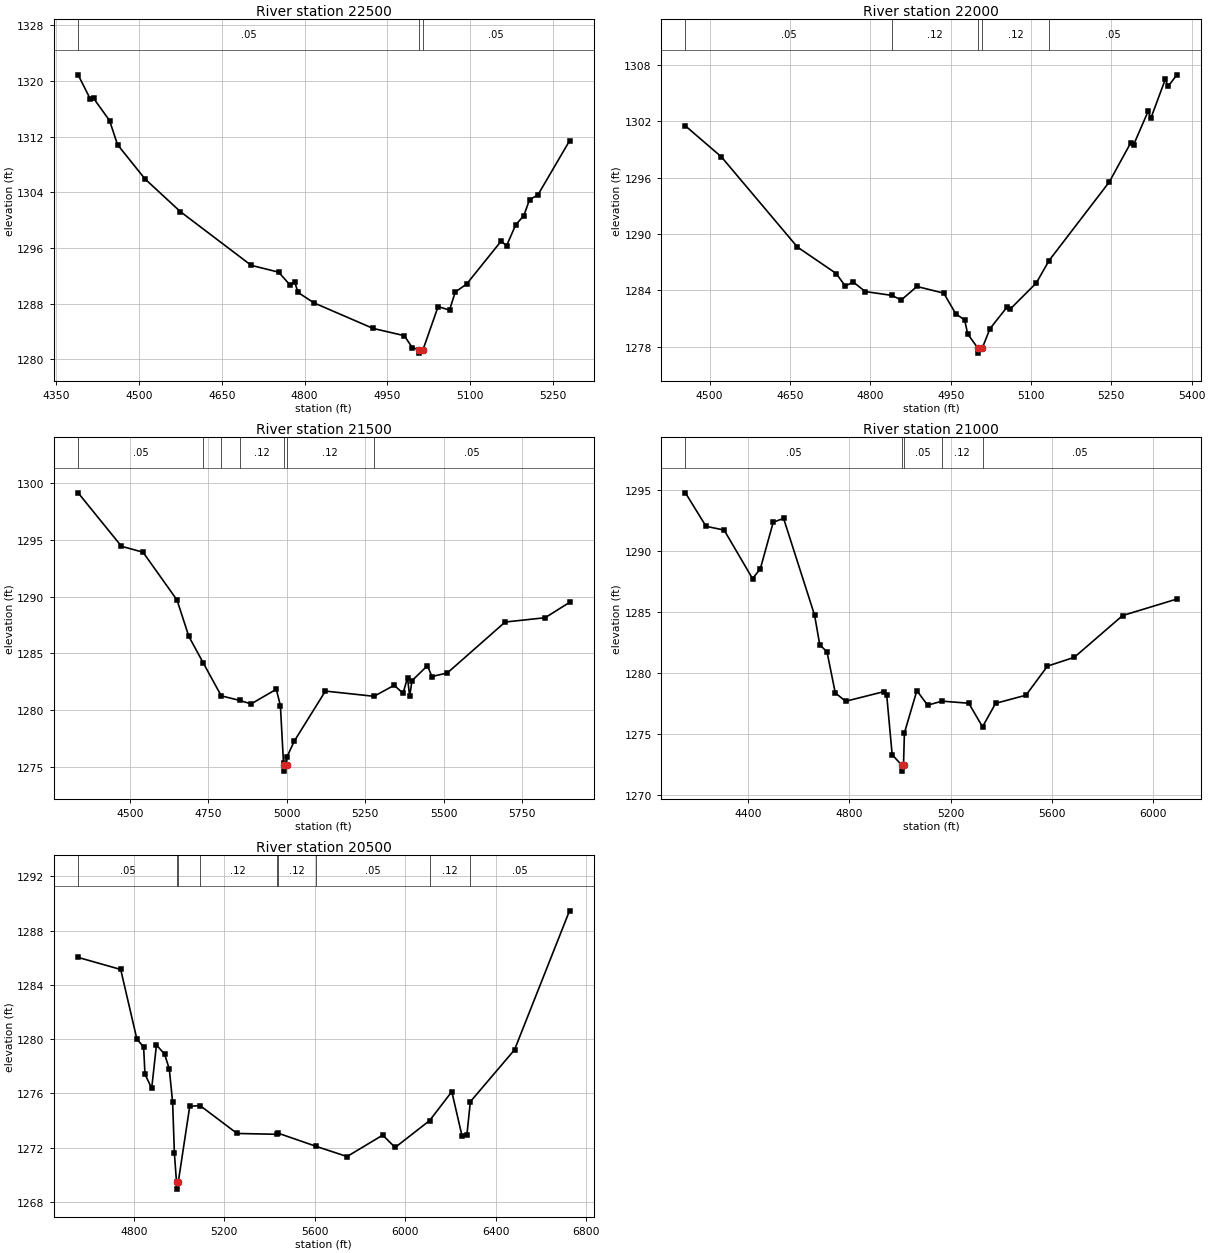
Type RM Length L Ch R = 1 ,22500   ,500,500,500
BEGIN DESCRIPTION:
LANG CREEK 44.0
END DESCRIPTION:
XS GIS Cut Line= 3
      2734355.65     10207203.14      2734835.13     10206825.72
      2735105.66     10206753.12
#Sta/Elev= 30
  4389.8 1320.88  4411.5 1317.46  4417.9  1317.5  4446.8  1314.3  4461.2 1310.84
  4510.9 1305.92  4575.1 1301.21  4703.4 1293.49  4753.1 1292.51  4773.9 1290.65
    4782 1291.13  4788.3 1289.59  4817.2 1288.09  4924.3 1284.42  4980.8 1283.38
  4995.2 1281.66  5007.2 1281.37  5007.7 1280.87  5014.7 1281.37    5042 1287.56
  5062.7 1287.06  5073.1 1289.65  5093.8 1290.81  5155.9 1296.94  5166.2 1296.33
  5182.7 1299.33  5197.3 1300.63  5207.7 1302.94  5222.7  1303.6  5280.1 1311.38
#Mann= 3 ,-1 , 0
  4389.8     .05       0  5007.2     .05       0  5014.7     .05       0
Bank Sta=5007.2,5014.7
XS Rating Curve= 0 ,0
Exp/Cntr=0.3,0.1

Type RM Length L Ch R = 1 ,22000   ,500,500,500
BEGIN DESCRIPTION:
LANG CREEK 43.0
END DESCRIPTION:
XS GIS Cut Line= 3
      2734655.67     10207453.12      2735142.67     10207207.79
       2735255.7     10206853.06
#Sta/Elev= 30
  4454.7 1301.53  4521.9 1298.23  4663.9 1288.62  4736.4  1285.8  4753.1 1284.47
  4768.2 1284.89  4790.6 1283.88  4840.2 1283.47  4857.8 1282.98    4887 1284.42
  4937.2 1283.71  4959.5 1281.51  4976.2 1280.85  4981.8 1279.36  5001.3 1277.82
  5001.8 1277.32  5008.8 1277.82  5023.5 1279.93  5055.7 1282.25    5061    1282
  5109.9 1284.79  5133.6 1287.17  5246.3 1295.56  5286.5 1299.75  5291.7 1299.52
  5318.7 1303.08  5323.9 1302.35  5350.9  1306.5  5356.1 1305.73  5372.3 1306.97
#Mann= 5 ,-1 , 0
  4454.7     .05       0  4840.2     .12       0  5001.3     .07       0
  5008.8     .12       0  5133.6     .05       0
Bank Sta=5001.3,5008.8
XS Rating Curve= 0 ,0
Exp/Cntr=0.3,0.1

Type RM Length L Ch R = 1 ,21500   ,500,500,500
BEGIN DESCRIPTION:
LANG CREEK 42.0
END DESCRIPTION:
XS GIS Cut Line= 3
      2734735.29     10207902.38      2735314.75     10207576.11
      2735967.73     10206955.14
#Sta/Elev= 30
    4335 1299.15  4473.2 1294.44  4541.9 1293.92  4650.2 1289.71  4687.8 1286.51
  4733.4 1284.19  4791.2 1281.27  4849.6 1280.87  4886.3 1280.56  4966.6 1281.85
  4979.7 1280.41  4989.6 1275.32  4991.9 1275.14  4992.4 1274.64  4999.4 1275.14
    5000 1275.86  5024.1 1277.29  5123.1 1281.69    5278 1281.23  5342.4  1282.2
  5370.7 1281.49  5384.8 1282.88  5391.7 1281.22    5399  1282.6  5448.4 1283.93
  5462.5 1282.97  5511.9 1283.29  5695.9 1287.77  5823.3 1288.15  5901.1  1289.5
#Mann= 7 ,-1 , 0
    4335     .05       0  4733.4     .12       0  4791.2     .05       0
  4849.6     .12       0  4991.9     .07       0  4999.4     .12       0
    5278     .05       0
Bank Sta=4991.9,4999.4
XS Rating Curve= 0 ,0
Exp/Cntr=0.3,0.1

Type RM Length L Ch R = 1 ,21000   ,500,500,500
BEGIN DESCRIPTION:
LANG CREEK 41.0
END DESCRIPTION:
XS GIS Cut Line= 3
      2734765.88      10208146.8      2735596.02     10207967.92
      2736334.43     10207158.81
#Sta/Elev= 30
  4150.8 1294.74  4232.4    1292    4304 1291.69  4416.6 1287.71  4447.3 1288.52
  4498.4 1292.33  4539.3 1292.65  4661.9 1284.73  4682.5  1282.3  4711.2 1281.71
  4743.9 1278.36  4784.8 1277.67  4938.3 1278.47  4947.5 1278.16    4969  1273.3
  5006.3 1272.45  5006.8 1271.95  5013.9 1272.45  5017.5 1275.08  5066.8 1278.54
  5109.4 1277.35  5166.2 1277.68  5272.2 1277.51  5326.6 1275.58  5378.3  1277.5
  5498.6 1278.17  5583.7 1280.55  5689.8 1281.27  5880.9 1284.69  6095.4 1286.04
#Mann= 5 ,-1 , 0
  4150.8     .05       0  5006.3     .05       0  5013.9     .05       0
  5166.2     .12       0  5326.6     .05       0
Bank Sta=5006.3,5013.9
XS Rating Curve= 0 ,0
Exp/Cntr=0.3,0.1

Type RM Length L Ch R = 1 ,20500   ,500,500,500
BEGIN DESCRIPTION:
LANG CREEK 40.0
END DESCRIPTION:
XS GIS Cut Line= 3
      2735295.49     10208605.15      2735662.75     10208350.87
      2737240.34     10207647.97
#Sta/Elev= 30
  4553.3 1286.02  4741.7 1285.13  4813.3    1280  4843.1 1279.42  4849.1 1277.41
  4878.9 1276.38  4899.8 1279.57  4935.6  1278.9  4956.6 1277.81  4971.4 1275.35
  4979.2 1271.59  4988.6 1269.45  4989.1 1268.95  4996.2 1269.45    5047 1275.04
  5092.4 1275.11  5256.5 1273.05  5431.5 1272.99  5436.4 1273.08  5606.4  1272.1
    5743 1271.35  5900.9 1272.93  5955.7 1272.02  6108.3    1274  6206.4 1276.13
  6251.3 1272.89  6273.1 1272.93  6288.4 1275.39  6483.8 1279.21  6727.1 1289.45
#Mann= 9 ,-1 , 0
  4553.3     .05       0  4988.6     .03       0  4996.2     .05       0
  5092.4     .12       0  5431.5     .05       0  5436.4     .12       0
  5606.4     .05       0  6108.3     .12       0  6288.4     .05       0
Bank Sta=4988.6,4996.2
XS Rating Curve= 0 ,0
Exp/Cntr=0.3,0.1