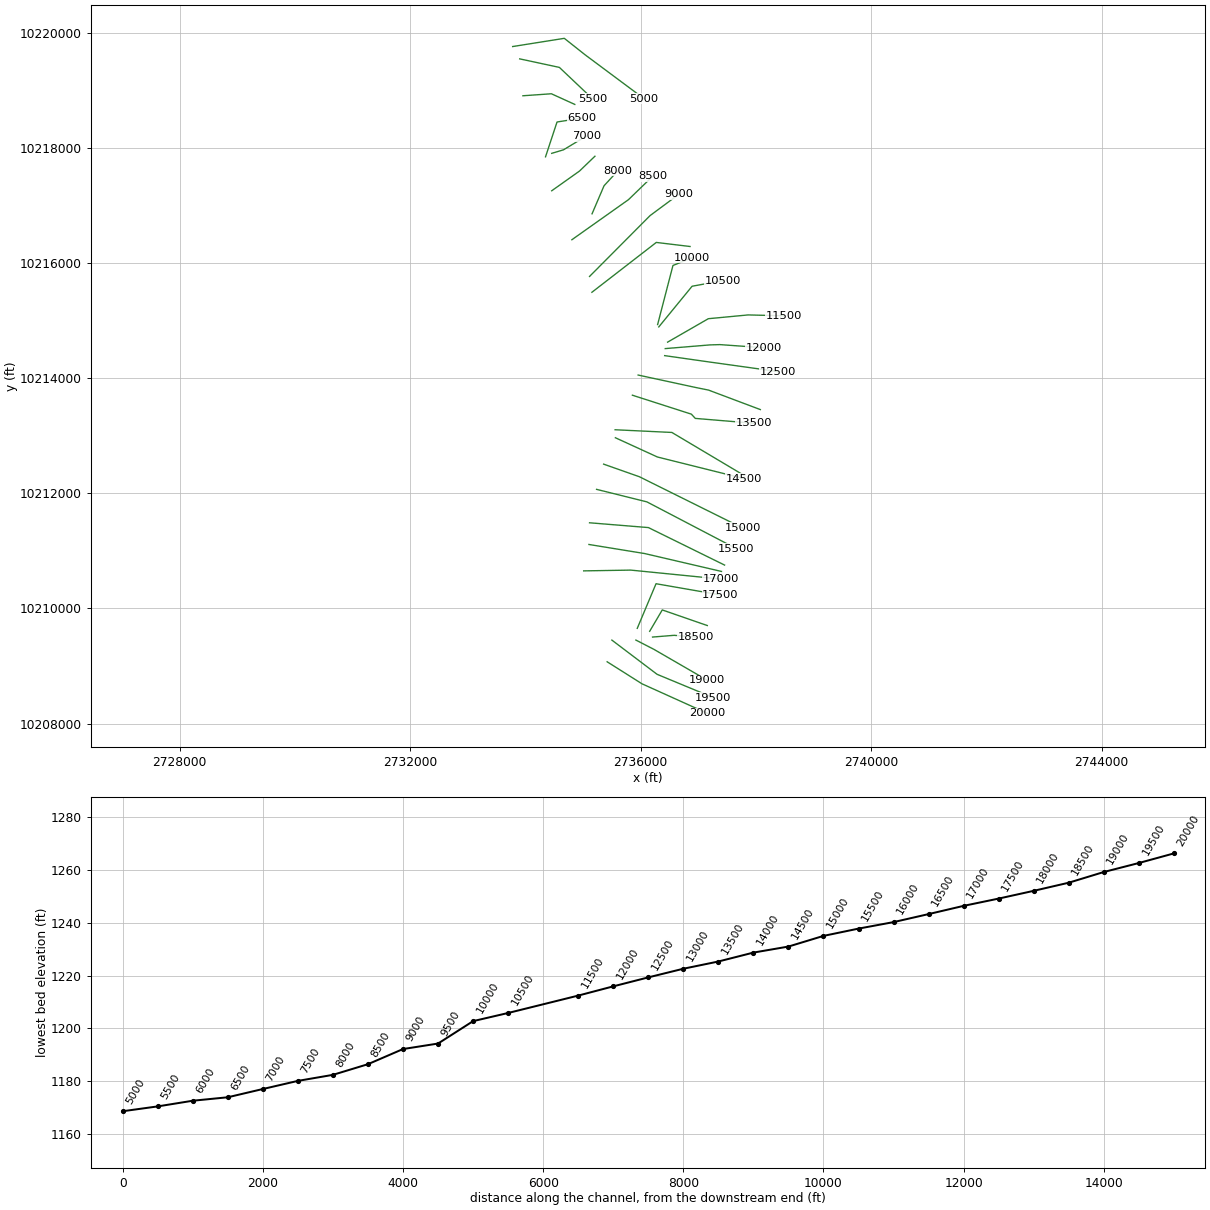
HEC-RAS study LANG CREEK.prj: LANG CREEK Base Level Engineering

--- LANG CREEK.g01 (geometry) --- (continued)

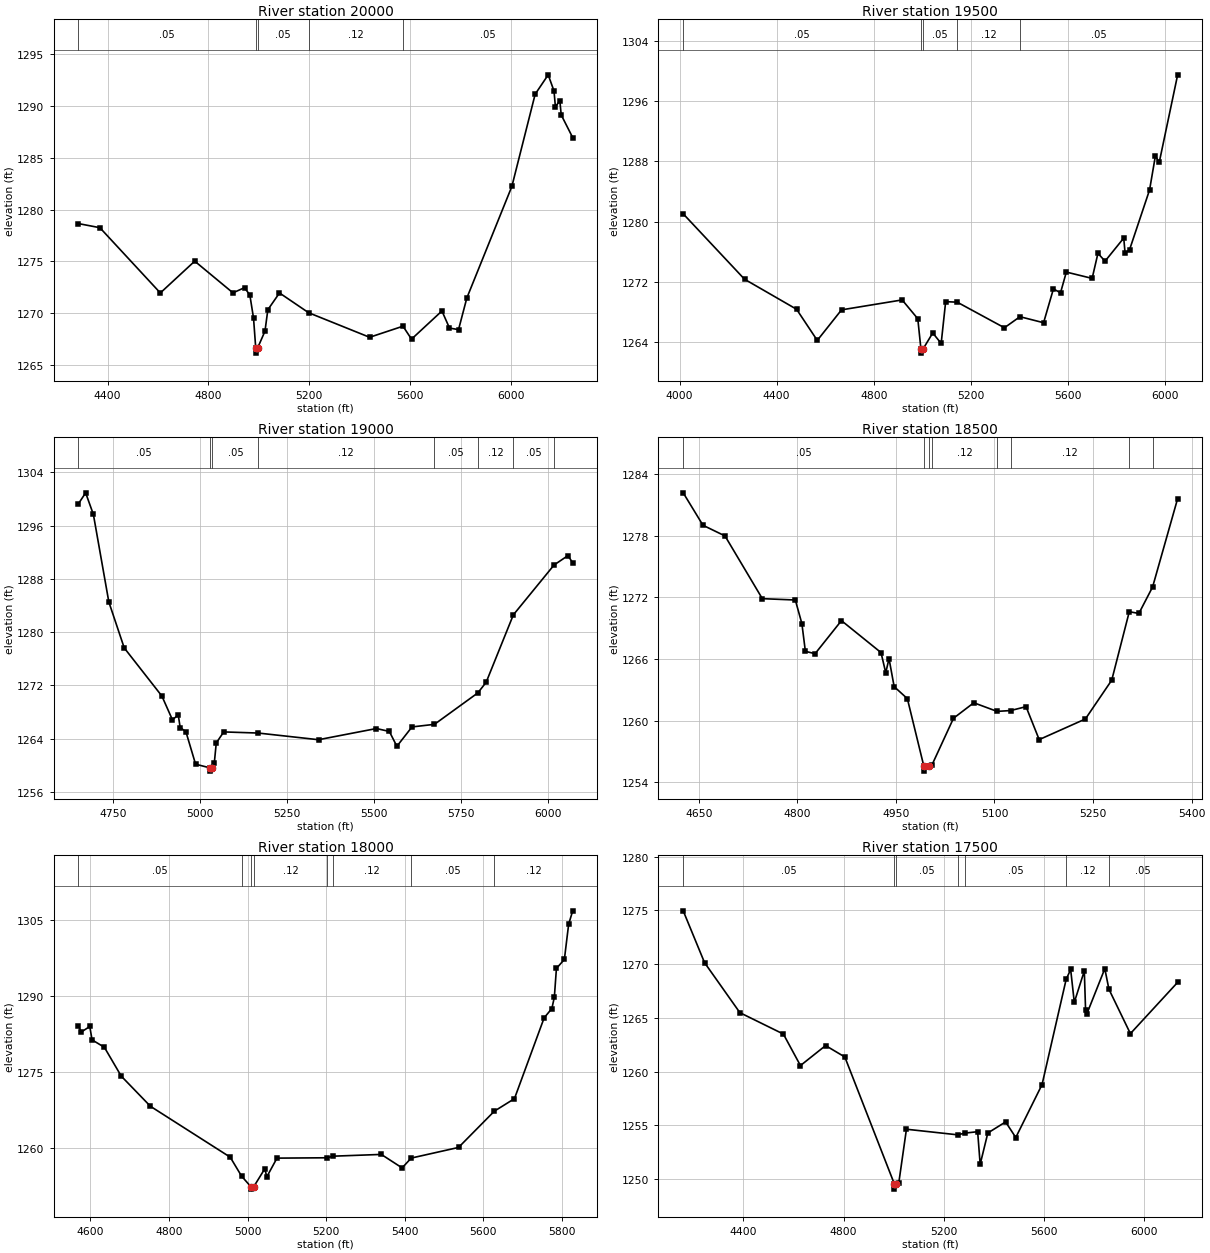
Type RM Length L Ch R = 1 ,20000   ,500,500,500
BEGIN DESCRIPTION:
LANG CREEK 39.0
END DESCRIPTION:
XS GIS Cut Line= 3
      2735417.73     10209073.66        2736023.     10208690.98
       2737158.6     10208177.72
#Sta/Elev= 30
  4283.9 1278.65  4369.7 1278.25  4609.6 1271.95  4746.1 1275.02  4897.9 1271.96
  4943.7 1272.46  4964.9 1271.75  4979.5 1269.52  4988.2 1266.64  4988.7 1266.14
  4995.8 1266.64  5024.9 1268.26  5036.3 1270.33  5082.5 1271.95  5198.2 1270.04
  5440.2 1267.67  5572.6 1268.74  5606.5 1267.49  5727.2 1270.21  5757.2 1268.56
  5793.1 1268.41    5826 1271.46  6004.8 1282.24  6097.2 1291.14  6148.9 1293.01
    6172 1291.45  6177.5 1289.93  6195.2 1290.51  6200.6 1289.14  6246.2 1286.95
#Mann= 5 ,-1 , 0
  4283.9     .05       0  4988.2     .05       0  4995.8     .05       0
  5198.2     .12       0  5572.6     .05       0
Bank Sta=4988.2,4995.8
XS Rating Curve= 0 ,0
Exp/Cntr=0.3,0.1

Type RM Length L Ch R = 1 ,19500   ,500,500,500
BEGIN DESCRIPTION:
LANG CREEK 38.0
END DESCRIPTION:
XS GIS Cut Line= 3
      2735499.18     10209450.53      2736284.43     10208855.88
      2737255.73     10208453.09
#Sta/Elev= 30
    4015 1281.02  4267.6 1272.33  4481.9 1268.34  4567.2  1264.2  4667.1 1268.26
  4916.8 1269.58  4981.2 1267.08  4994.3 1263.01  4994.8 1262.51  5001.9 1263.01
  5042.8 1265.19  5077.5  1263.8    5096 1269.35  5143.7 1269.28    5338 1265.88
    5402 1267.35  5499.3 1266.55  5539.8 1271.04  5569.1 1270.53    5593 1273.28
  5699.3 1272.44  5723.2 1275.77  5752.5 1274.73  5829.5  1277.8    5835 1275.79
  5853.4 1276.25  5935.9  1284.2  5959.8 1288.71  5975.7 1287.86  6051.5 1299.49
#Mann= 5 ,-1 , 0
    4015     .05       0  4994.3     .05       0  5001.9     .05       0
  5143.7     .12       0    5402     .05       0
Bank Sta=4994.3,5001.9
XS Rating Curve= 0 ,0
Exp/Cntr=0.3,0.1

Type RM Length L Ch R = 1 ,19000   ,500,500,500
BEGIN DESCRIPTION:
LANG CREEK 37.0
END DESCRIPTION:
XS GIS Cut Line= 3
      2735916.79     10209450.51      2736228.19     10209290.28
      2737155.66     10208753.12
#Sta/Elev= 30
  4649.8 1299.24    4671 1300.92  4693.3 1297.67  4737.7 1284.53    4782 1277.62
  4890.3 1270.39  4920.7 1266.81  4937.3 1267.57  4942.9 1265.66  4959.4 1265.03
  4987.2 1260.15  5027.9 1259.61  5028.4 1259.11  5035.6 1259.61  5040.9 1260.26
  5046.7 1263.35  5068.2    1265  5167.5 1264.83  5340.8 1263.83  5507.3 1265.51
  5544.5 1265.07  5566.1 1262.84  5609.6 1265.75  5674.2 1266.14  5798.9 1270.86
  5822.9 1272.46  5901.1 1282.59  6018.2 1290.08  6058.2 1291.49  6071.8  1290.4
#Mann= 8 ,-1 , 0
  4649.8     .05       0  5027.9     .05       0  5035.6     .05       0
  5167.5     .12       0  5674.2     .05       0  5798.9     .12       0
  5901.1     .05       0  6018.2     .12       0
Bank Sta=5027.9,5035.6
XS Rating Curve= 0 ,0
Exp/Cntr=0.3,0.1

Type RM Length L Ch R = 1 ,18500   ,500,500,500
BEGIN DESCRIPTION:
LANG CREEK 36.0
END DESCRIPTION:
XS GIS Cut Line= 3
      2736205.68     10209503.11      2736578.17     10209533.22
      2736955.67     10209503.11
#Sta/Elev= 30
  4626.3 1282.18  4656.4 1279.02  4689.9 1277.98  4746.7 1271.87  4796.9 1271.74
  4806.9 1269.44  4812.2 1266.74    4827 1266.51  4867.1 1269.73  4927.3 1266.62
  4934.5 1264.65  4939.5 1266.03  4947.3  1263.3  4967.4 1262.13  4992.4 1255.57
  4992.9 1255.07  5000.1 1255.57  5004.5 1255.62  5037.6 1260.22  5068.5 1261.73
  5103.9 1260.89  5124.5 1260.97    5148 1261.35    5168 1258.14  5238.3 1260.15
  5278.4 1263.93  5305.1  1270.6  5319.7 1270.43  5340.6 1273.01  5378.7 1281.62
#Mann= 8 ,-1 , 0
  4626.3     .05       0  4992.4     .05       0  5000.1     .05       0
  5004.5     .12       0  5103.9     .05       0  5124.5     .12       0
  5305.1     .05       0  5340.6     .12       0
Bank Sta=4992.4,5000.1
XS Rating Curve= 0 ,0
Exp/Cntr=0.3,0.1

Type RM Length L Ch R = 1 ,18000   ,500,500,500
BEGIN DESCRIPTION:
LANG CREEK 35.0
END DESCRIPTION:
XS GIS Cut Line= 3
      2736155.68      10209603.1      2736374.19     10209974.15
      2737155.72      10209703.1
#Sta/Elev= 30
  4569.4 1284.16  4577.2 1282.92  4598.7    1284  4604.5 1281.37  4635.8 1279.91
  4678.7 1274.24    4753  1268.3  4955.9 1258.29  4984.9 1254.55  5008.3  1252.5
  5008.8    1252    5016  1252.5  5043.8 1255.99  5049.1 1254.43  5074.9  1258.1
  5203.4 1258.17  5216.7 1258.48  5340.3 1258.83  5393.2 1256.18  5416.4 1258.11
  5536.7  1260.2  5627.9 1267.34    5679  1269.8  5754.6 1285.71  5774.2 1287.54
  5780.5 1289.76  5785.8 1295.43    5806 1297.19  5816.9 1304.13  5827.2 1306.76
#Mann= 8 ,-1 , 0
  4569.4     .05       0  4984.9     .12       0  5008.3     .07       0
    5016     .12       0  5203.4     .05       0  5216.7     .12       0
  5416.4     .05       0  5627.9     .12       0
Bank Sta=5008.3,5016
XS Rating Curve= 0 ,0
Exp/Cntr=0.3,0.1

Type RM Length L Ch R = 1 ,17500   ,500,500,500
BEGIN DESCRIPTION:
LANG CREEK 34.0
END DESCRIPTION:
XS GIS Cut Line= 3
      2735940.35     10209654.54      2736265.97     10210429.29
      2737382.09       10210235.
#Sta/Elev= 30
  4159.6 1274.95  4244.8 1270.13  4385.8 1265.48  4559.4 1263.49  4627.5 1260.56
  4727.9 1262.42  4804.6 1261.36    5002 1249.57  5002.5 1249.07  5009.7 1249.57
    5020 1249.65  5050.5 1254.64    5255 1254.12  5283.9 1254.28  5334.7 1254.41
  5344.8 1251.38  5375.3 1254.29  5446.3 1255.32  5486.9 1253.87  5591.7 1258.79
  5687.9 1268.57  5705.9  1269.5  5720.4 1266.44  5760.4 1269.36  5765.5  1265.7
  5771.1  1265.4  5842.2 1269.57  5858.6 1267.66  5944.3 1263.53  6132.9  1268.3
#Mann= 7 ,-1 , 0
  4159.6     .05       0    5002     .05       0  5009.7     .05       0
    5255     .12       0  5283.9     .05       0  5687.9     .12       0
  5858.6     .05       0
Bank Sta=5002,5009.7
XS Rating Curve= 0 ,0
Exp/Cntr=0.3,0.1

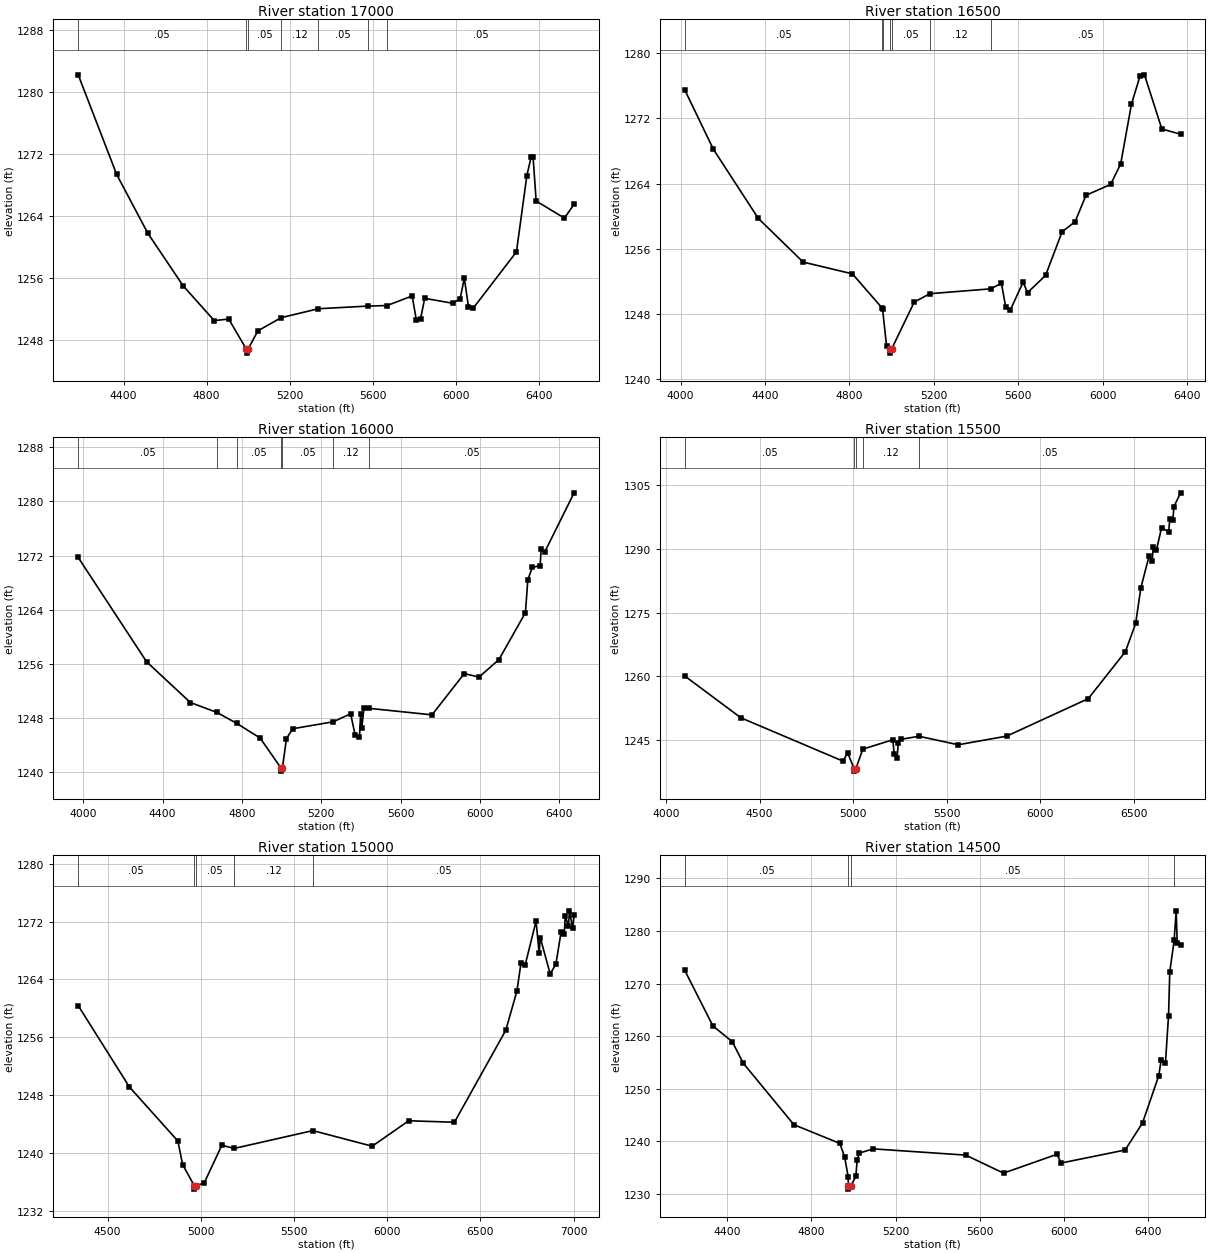
Type RM Length L Ch R = 1 ,17000   ,500,500,500
BEGIN DESCRIPTION:
LANG CREEK 33.0
END DESCRIPTION:
XS GIS Cut Line= 3
       2735010.3     10210652.35      2735828.59     10210665.73
      2737392.15     10210509.91
#Sta/Elev= 30
  4181.6 1282.18    4367 1269.34    4517 1261.77  4687.1    1255  4837.1 1250.51
  4907.1 1250.71  4992.1 1246.82  4992.6 1246.32  4999.9 1246.82  5047.3 1249.19
  5159.8 1250.89    5339 1252.04  5576.3 1252.38  5669.7 1252.45    5791 1253.69
  5811.1 1250.58  5831.2 1250.71  5851.3 1253.38  5985.7 1252.75  6022.1 1253.32
  6042.2 1255.97  6062.3 1252.32  6086.3 1252.15  6293.5 1259.37  6343.7 1269.19
  6363.8 1271.55  6373.9 1271.53  6388.4 1265.92  6524.6 1263.72  6571.3  1265.5
#Mann= 7 ,-1 , 0
  4181.6     .05       0  4992.1     .05       0  4999.9     .05       0
  5159.8     .12       0    5339     .05       0  5576.3     .12       0
  5669.7     .05       0
Bank Sta=4992.1,4999.9
XS Rating Curve= 0 ,0
Exp/Cntr=0.3,0.1

Type RM Length L Ch R = 1 ,16500   ,500,500,500
BEGIN DESCRIPTION:
LANG CREEK 32.0
END DESCRIPTION:
XS GIS Cut Line= 3
      2735101.95      10211110.7      2736069.31     10210953.17
      2737402.29     10210642.53
#Sta/Elev= 30
  4019.9 1275.49  4155.4 1268.21  4368.2 1259.73  4580.9 1254.37    4814 1252.93
  4956.5 1248.69  4956.8 1248.65  4976.1 1244.05  4991.5 1243.71    4992 1243.21
  4999.7 1243.71  5107.2 1249.48  5181.8  1250.5  5468.3 1251.09  5519.9 1251.76
  5540.5 1248.83    5561 1248.44  5622.6  1251.9  5643.7 1250.63  5728.8 1252.73
  5807.4 1258.09  5869.1 1259.33  5920.4 1262.56  6037.1 1263.89  6084.8 1266.41
    6136 1273.76  6177.1 1277.24  6197.6 1277.33  6279.8 1270.69  6368.7 1270.05
#Mann= 7 ,-1 , 0
  4019.9     .05       0  4956.5     .12       0  4956.8     .05       0
  4991.5     .05       0  4999.7     .05       0  5181.8     .12       0
  5468.3     .05       0
Bank Sta=4991.5,4999.7
XS Rating Curve= 0 ,0
Exp/Cntr=0.3,0.1

Type RM Length L Ch R = 1 ,16000   ,500,500,500
BEGIN DESCRIPTION:
LANG CREEK 31.0
END DESCRIPTION:
XS GIS Cut Line= 3
      2735112.22     10211487.54      2736133.63     10211404.27
      2737455.67     10210753.12
#Sta/Elev= 30
  3975.2 1271.73  4319.8 1256.33  4540.5 1250.31  4673.9 1248.85  4773.4 1247.24
  4891.7 1245.07  4995.9 1240.68  4996.4 1240.18  5004.1 1240.68  5024.6 1244.98
  5055.8 1246.44  5260.8 1247.47  5347.8 1248.65  5370.1 1245.55  5392.4  1245.2
  5398.3 1248.62  5403.9 1246.55  5414.7 1249.45  5438.7 1249.46  5757.8 1248.49
  5920.6 1254.59  5994.4 1254.06  6094.7 1256.64  6228.5 1263.58  6240.6 1268.44
  6263.1 1270.26  6302.5 1270.53    6308 1273.02  6324.9 1272.49  6473.7 1281.28
#Mann= 7 ,-1 , 0
  3975.2     .05       0  4673.9     .12       0  4773.4     .05       0
  4995.9     .05       0  5004.1     .05       0  5260.8     .12       0
  5438.7     .05       0
Bank Sta=4995.9,5004.1
XS Rating Curve= 0 ,0
Exp/Cntr=0.3,0.1

Type RM Length L Ch R = 1 ,15500   ,500,500,500
BEGIN DESCRIPTION:
LANG CREEK 30.0
END DESCRIPTION:
XS GIS Cut Line= 3
      2735234.44     10212068.09      2736107.95      10211850.5
      2737658.51     10211039.38
#Sta/Elev= 30
  4099.8  1260.1  4399.9 1250.26  4946.1 1240.06  4970.2 1242.04  5005.6 1238.22
  5006.1 1237.72  5013.9 1238.22  5051.4 1242.89  5211.9  1245.1  5219.2 1241.65
  5234.4 1240.72  5241.3 1244.39    5257 1245.21  5351.4 1245.92  5561.1 1243.92
  5820.3 1245.95  6256.1 1254.76  6454.8 1265.82  6509.7 1272.46  6537.4 1280.82
  6581.6 1288.36    6598 1287.23  6603.6 1290.44  6620.1 1289.67  6647.8 1294.88
  6686.3 1294.07  6691.9 1296.95  6708.3 1296.74    6714 1299.93  6749.9 1303.17
#Mann= 5 ,-1 , 0
  4099.8     .05       0  5005.6     .05       0  5013.9     .05       0
  5051.4     .12       0  5351.4     .05       0
Bank Sta=5005.6,5013.9
XS Rating Curve= 0 ,0
Exp/Cntr=0.3,0.1

Type RM Length L Ch R = 1 ,15000   ,500,500,500
BEGIN DESCRIPTION:
LANG CREEK 29.0
END DESCRIPTION:
XS GIS Cut Line= 3
       2735356.6     10212506.07      2735977.02     10212287.18
      2737770.55     10211395.86
#Sta/Elev= 30
  4342.1 1260.37  4616.8 1249.11  4876.8 1241.63  4902.4 1238.36  4964.4 1235.47
  4964.9 1234.97  4974.9 1235.47  5017.8 1235.81    5113 1241.05  5178.6  1240.6
  5601.1 1243.07  5919.5 1240.91  6115.2 1244.43  6360.9 1244.23  6636.3 1256.96
  6695.9 1262.37  6718.2 1266.32  6740.5 1266.02  6798.7 1272.06  6815.5 1267.59
  6821.1 1269.79  6874.5 1264.76  6905.2 1266.11  6933.1 1270.57    6950 1270.26
  6955.5 1272.75  6972.4 1271.41  6977.9 1273.49  6994.8 1271.12  7002.8 1272.89
#Mann= 5 ,-1 , 0
  4342.1     .05       0  4964.4     .03       0  4974.9     .05       0
  5178.6     .12       0  5601.1     .05       0
Bank Sta=4964.4,4974.9
XS Rating Curve= 0 ,0
Exp/Cntr=0.3,0.1

Type RM Length L Ch R = 1 ,14500   ,500,500,500
BEGIN DESCRIPTION:
LANG CREEK 28.0
END DESCRIPTION:
XS GIS Cut Line= 3
      2735560.31      10212964.4      2736289.12     10212630.39
      2737795.63     10212254.08
#Sta/Elev= 30
  4198.3 1272.51  4332.1 1261.94  4424.1 1258.95  4475.6 1254.89  4716.6 1243.18
  4934.6 1239.63  4957.6 1237.05  4974.2 1233.31  4975.3 1231.44  4975.8 1230.94
  4985.8 1231.44  5010.7 1233.37  5017.1 1236.56  5027.4 1237.79  5093.2 1238.59
  5532.4  1237.4  5711.9 1233.98  5965.3 1237.55    5986  1235.9  6289.3 1238.37
  6371.8 1243.51  6449.1 1252.49  6460.1 1255.42  6480.7 1254.91  6495.5 1263.92
  6501.3 1272.23    6522 1278.18  6531.6 1283.81  6536.8 1277.61  6552.8  1277.4
#Mann= 4 ,-1 , 0
  4198.3     .05       0  4975.3     .05       0  4985.8     .05       0
    6522     .12       0
Bank Sta=4975.3,4985.8
XS Rating Curve= 0 ,0
Exp/Cntr=0.3,0.1

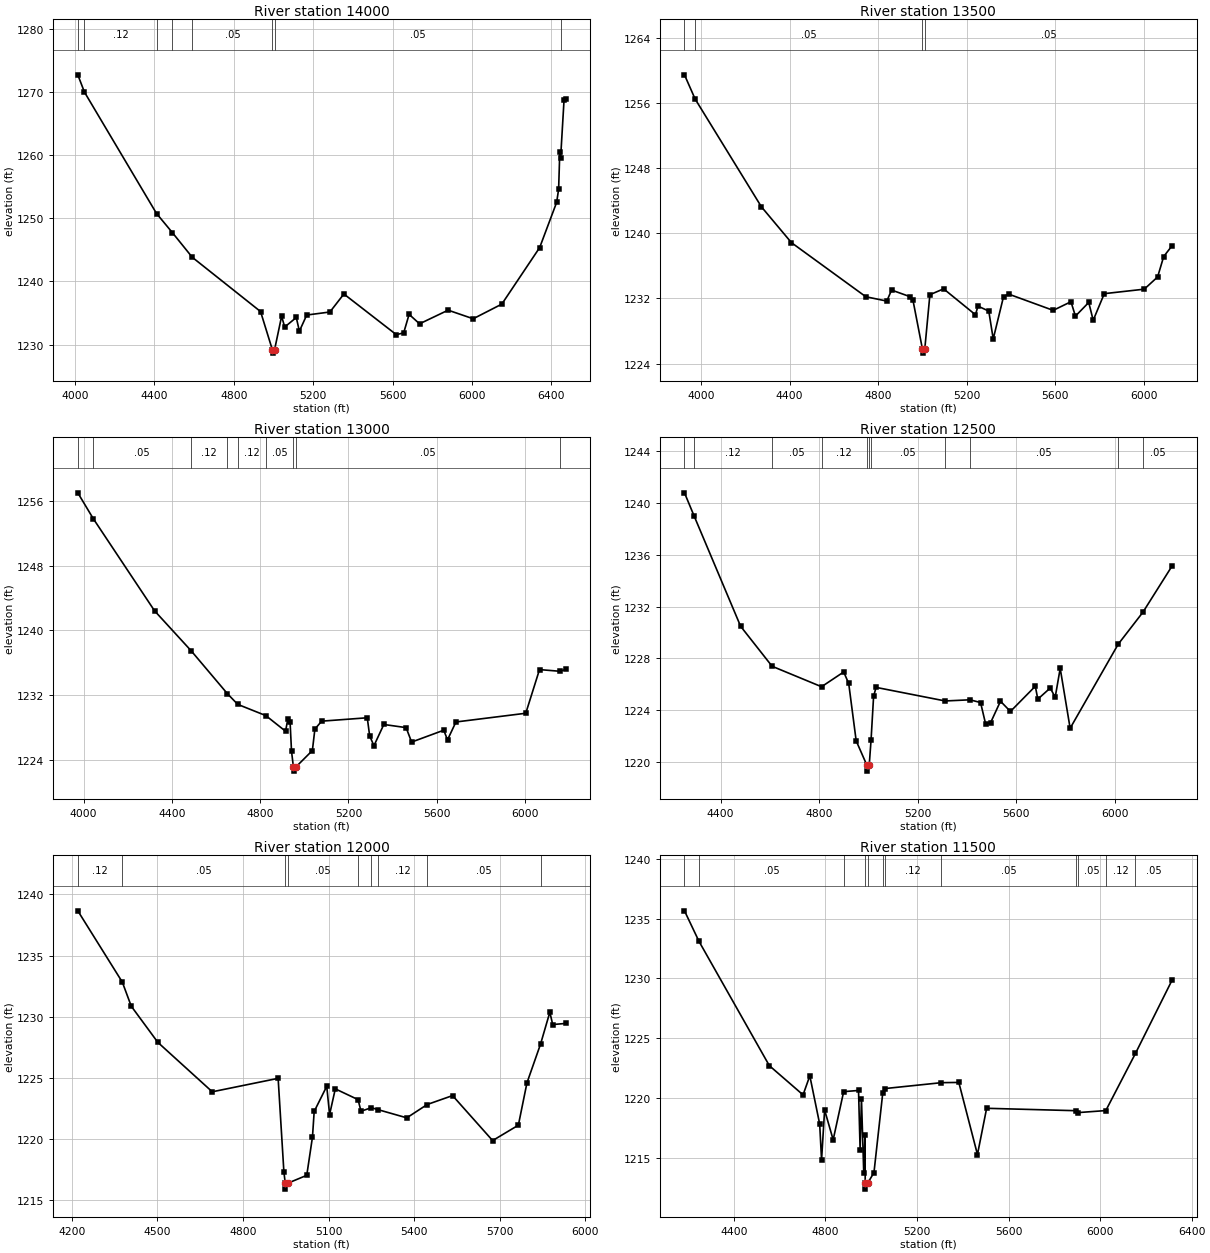
Type RM Length L Ch R = 1 ,14000   ,500,500,500
BEGIN DESCRIPTION:
LANG CREEK 27.0
END DESCRIPTION:
XS GIS Cut Line= 3
      2735555.66     10213103.11      2736540.75     10213056.28
       2737805.7      10212303.1
#Sta/Elev= 30
  4013.8 1272.71  4047.2 1269.98  4410.6 1250.76  4490.3 1247.74  4590.7 1243.83
  4934.9 1235.24  4994.7 1229.16  4995.2 1228.66  5005.3 1229.16    5041  1234.5
  5056.6 1232.79    5115  1234.3  5130.6 1232.14  5167.6 1234.69  5284.4 1235.17
  5354.9 1238.02  5619.3 1231.58  5656.3 1231.87  5683.6  1234.8  5736.2  1233.3
  5880.2 1235.46  6006.6  1234.1  6150.9 1236.42  6341.7 1245.37  6427.4 1252.54
  6437.2 1254.61    6443 1260.45  6447.3  1259.6  6464.4 1268.67  6472.2 1268.92
#Mann= 8 ,-1 , 0
  4013.8     .05       0  4047.2     .12       0  4410.6     .05       0
  4490.3     .12       0  4590.7     .05       0  4994.7     .03       0
  5005.3     .05       0  6447.3     .12       0
Bank Sta=4994.7,5005.3
XS Rating Curve= 0 ,0
Exp/Cntr=0.3,0.1

Type RM Length L Ch R = 1 ,13500   ,500,500,500
BEGIN DESCRIPTION:
LANG CREEK 26.0
END DESCRIPTION:
XS GIS Cut Line= 4
      2735855.69     10213703.11      2736879.29     10213374.02
      2736947.16     10213300.27       2737971.6     10213215.12
#Sta/Elev= 30
  3924.8 1259.45  3972.7 1256.49  4272.3 1243.25    4408 1238.85  4744.1 1232.21
  4838.7 1231.68  4860.4 1233.03  4943.7 1232.22  4956.7 1231.82  4999.7 1225.79
  5000.2 1225.29  5010.3 1225.79  5033.4 1232.46  5095.4 1233.18  5239.2    1230
  5250.6 1231.06  5299.4 1230.45  5319.5 1227.03  5366.2 1232.24  5389.7 1232.53
  5590.4 1230.54  5670.7  1231.6  5690.8 1229.83    5751 1231.51  5771.1 1229.32
  5821.2 1232.59  6001.8 1233.14  6062.1 1234.64  6089.6 1237.15  6128.2  1238.5
#Mann= 4 ,-1 , 0
  3924.8     .12       0  3972.7     .05       0  4999.7     .05       0
  5010.3     .05       0
Bank Sta=4999.7,5010.3
XS Rating Curve= 0 ,0
Exp/Cntr=0.3,0.1

Type RM Length L Ch R = 1 ,13000   ,500,500,500
BEGIN DESCRIPTION:
LANG CREEK 25.0
END DESCRIPTION:
XS GIS Cut Line= 4
       2735955.7     10214053.11       2736958.6     10213836.15
      2737176.83     10213792.03      2738076.24     10213453.36
#Sta/Elev= 30
  3973.9 1257.04  4043.7 1253.85  4321.7 1242.42  4487.1 1237.48  4651.8 1232.15
  4698.5 1230.83  4825.8 1229.44  4915.2  1227.5  4925.4 1229.03  4935.6 1228.66
  4942.1 1225.04  4950.7 1223.06  4951.2 1222.56  4961.4 1223.06  5036.6 1225.11
    5048 1227.77  5078.6 1228.75  5285.3 1229.17  5296.2 1226.92  5315.6 1225.71
  5360.3 1228.34  5461.3 1227.95  5486.2 1226.16  5631.9 1227.63  5648.8 1226.43
    5687 1228.65  6003.4 1229.73  6065.6 1235.14  6158.4 1234.93  6183.7 1235.16
#Mann= 9 ,-1 , 0
  3973.9     .12       0  4043.7     .05       0  4487.1     .12       0
  4651.8     .05       0  4698.5     .12       0  4825.8     .05       0
  4950.7     .05       0  4961.4     .05       0  6158.4     .12       0
Bank Sta=4950.7,4961.4
XS Rating Curve= 0 ,0
Exp/Cntr=0.3,0.1

Type RM Length L Ch R = 1 ,12500   ,500,500,500
BEGIN DESCRIPTION:
LANG CREEK 24.0
END DESCRIPTION:
XS GIS Cut Line= 3
      2736415.88     10214390.32      2737155.23     10214285.06
      2738376.08     10214114.51
#Sta/Elev= 30
  4253.2 1240.79  4292.1 1239.01    4481 1230.48  4608.8 1227.39  4809.5 1225.81
  4899.4 1226.95  4919.7 1226.06    4950 1221.63  4992.4 1219.79  4992.9 1219.29
  5003.1 1219.79  5010.3 1221.67  5020.7 1225.07  5030.7 1225.76  5311.2 1224.71
  5411.5  1224.8  5454.8 1224.59    5475 1222.96  5495.2 1223.02  5535.6 1224.69
    5576  1223.9    5677 1225.85  5687.1 1224.85  5737.5 1225.71  5757.7    1225
    5778 1227.23  5818.3  1222.6  6013.5  1229.1  6113.8 1231.57  6232.7 1235.16
#Mann= 11 ,-1 , 0
  4253.2     .05       0  4292.1     .12       0  4608.8     .05       0
  4809.5     .12       0  4992.4     .07       0  5003.1     .12       0
  5010.3     .05       0  5311.2     .12       0  5411.5     .05       0
  6013.5     .12       0  6113.8     .05       0
Bank Sta=4992.4,5003.1
XS Rating Curve= 0 ,0
Exp/Cntr=0.3,0.1

Type RM Length L Ch R = 1 ,12000   ,500,500,500
BEGIN DESCRIPTION:
LANG CREEK 23.0
END DESCRIPTION:
XS GIS Cut Line= 4
      2736426.06     10214512.54      2737202.13     10214576.56
       2737372.6     10214581.78      2738130.65     10214528.11
#Sta/Elev= 30
  4221.3 1238.66  4377.3 1232.83  4408.6 1230.86  4501.9  1227.9  4692.5 1223.86
  4923.3 1224.96  4943.4 1217.33  4948.1  1216.4  4948.6  1215.9  4958.8  1216.4
  5023.6 1217.03  5043.6 1220.16  5049.6 1222.25  5093.6 1224.31  5103.6    1222
  5123.6  1224.1  5203.3 1223.22  5213.7 1222.27  5249.8 1222.56  5274.8 1222.39
  5374.1 1221.73  5445.6 1222.82  5534.5 1223.55  5674.9 1219.87  5765.1 1221.13
  5795.2 1224.59  5842.8 1227.76  5875.4 1230.37  5885.4 1229.36  5930.5 1229.45
#Mann= 9 ,-1 , 0
  4221.3     .12       0  4377.3     .05       0  4948.1     .03       0
  4958.8     .05       0  5203.3     .12       0  5249.8     .05       0
  5274.8     .12       0  5445.6     .05       0  5842.8     .12       0
Bank Sta=4948.1,4958.8
XS Rating Curve= 0 ,0
Exp/Cntr=0.3,0.1

Type RM Length L Ch R = 1 ,11500   ,1000,1000,1000
BEGIN DESCRIPTION:
LANG CREEK 22.0
END DESCRIPTION:
XS GIS Cut Line= 4
      2736466.82     10214624.58       2737173.5     10215031.57
      2737864.91     10215097.15      2738485.42     10215082.17
#Sta/Elev= 30
  4184.5 1235.65  4247.9  1233.1  4555.2 1222.72  4702.5 1220.28    4732 1221.87
  4775.1 1217.84  4783.3 1214.84  4796.6 1219.02    4834 1216.53  4879.8 1220.55
  4944.8 1220.65  4951.8 1215.65  4957.6 1219.97  4967.6 1213.76  4973.3 1216.89
    4974 1212.91  4974.5 1212.41  4984.8 1212.91  5012.2 1213.79  5050.7 1220.45
  5061.2 1220.81  5307.1  1221.3  5382.9 1221.32  5464.3  1215.3  5504.4 1219.16
  5892.9 1218.96  5903.1  1218.8    6025 1218.97  6154.4 1223.74  6315.2 1229.89
#Mann= 12 ,-1 , 0
  4184.5     .12       0  4247.9     .05       0  4879.8     .12       0
    4974     .07       0  4984.8     .12       0  5050.7     .05       0
  5061.2     .12       0  5307.1     .05       0  5892.9     .12       0
  5903.1     .05       0    6025     .12       0  6154.4     .05       0
Bank Sta=4974,4984.8
XS Rating Curve= 0 ,0
Exp/Cntr=0.3,0.1

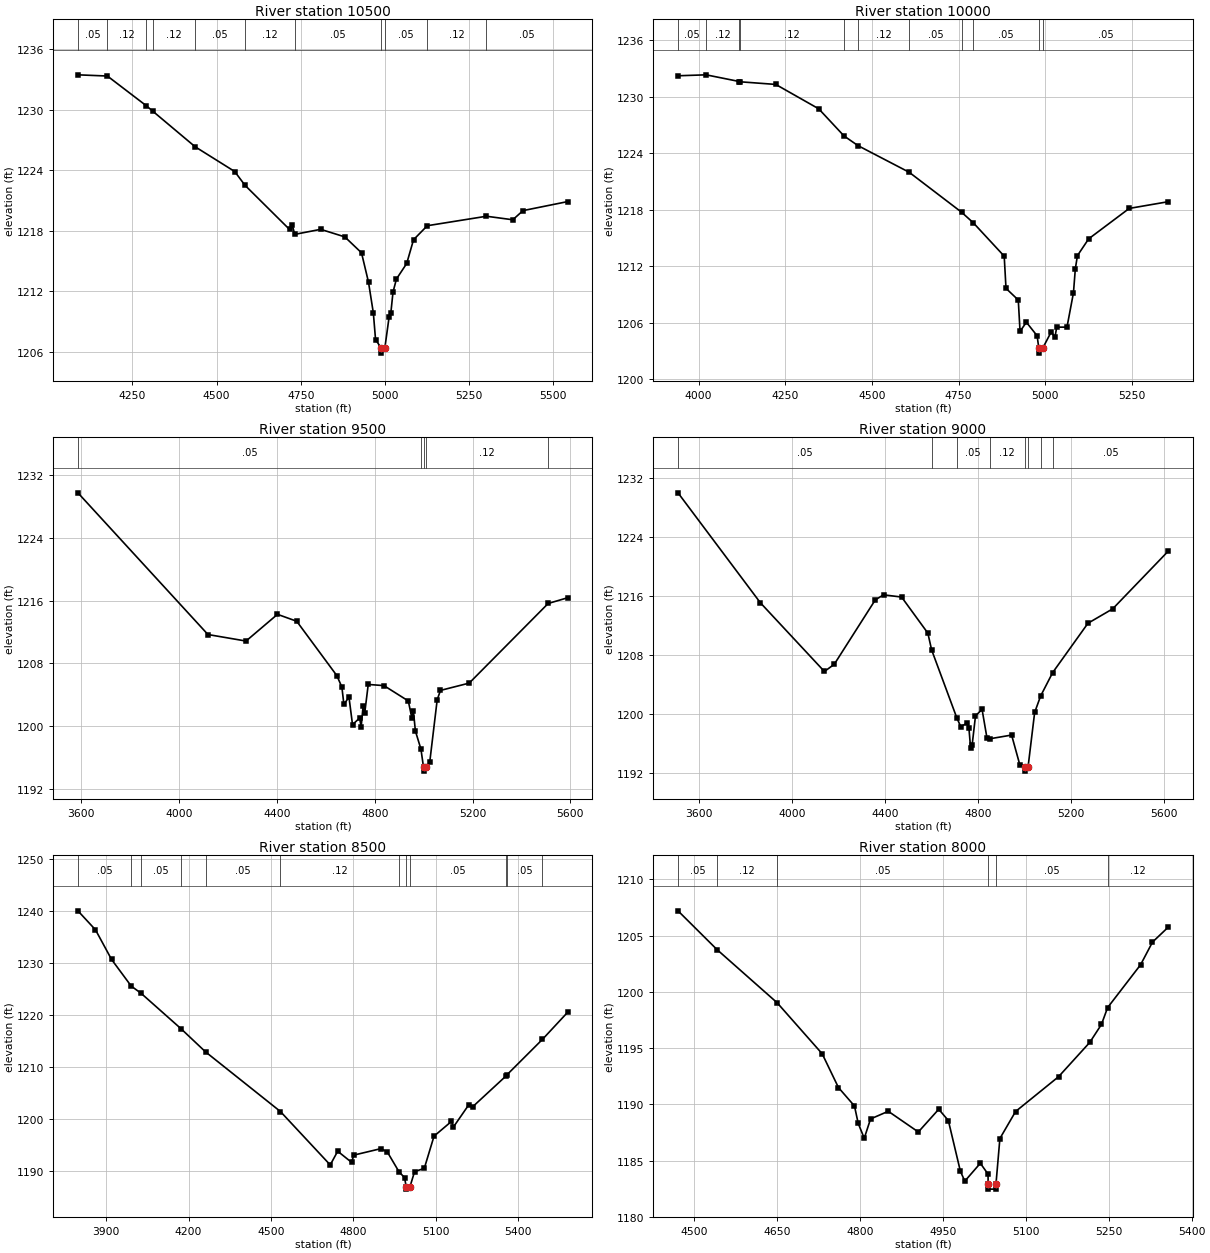
Type RM Length L Ch R = 1 ,10500   ,500,500,500
BEGIN DESCRIPTION:
LANG CREEK 21.0
END DESCRIPTION:
XS GIS Cut Line= 3
      2736314.07     10214889.43      2736891.85     10215595.18
       2737426.9      10215693.5
#Sta/Elev= 30
  4087.9 1233.47  4175.5 1233.35  4290.4 1230.42  4310.7 1229.85  4436.2 1226.33
  4553.8 1223.87  4584.2 1222.51  4716.7 1218.12  4724.6 1218.57  4732.2 1217.63
  4809.3 1218.13    4881 1217.38  4930.6  1215.8  4951.4 1212.88  4965.8 1209.82
  4972.3 1207.19  4989.1 1206.34  4989.6 1205.84  4999.9 1206.34  5012.6 1209.43
  5017.7 1209.81  5024.2  1211.9  5034.4  1213.2  5064.9 1214.74  5085.2  1217.1
  5126.1 1218.49  5301.9 1219.43  5380.1 1219.08  5410.6 1219.99    5544 1220.89
#Mann= 11 ,-1 , 0
  4087.9     .05       0  4175.5     .12       0  4290.4     .05       0
  4310.7     .12       0  4436.2     .05       0  4584.2     .12       0
  4732.2     .05       0  4989.1     .05       0  4999.9     .05       0
  5126.1     .12       0  5301.9     .05       0
Bank Sta=4989.1,4999.9
XS Rating Curve= 0 ,0
Exp/Cntr=0.3,0.1

Type RM Length L Ch R = 1 ,10000   ,500,500,500
BEGIN DESCRIPTION:
LANG CREEK 20.0
END DESCRIPTION:
XS GIS Cut Line= 3
      2736293.67     10214930.16      2736559.65     10215955.83
      2736887.87     10216088.71
#Sta/Elev= 30
  3940.4 1232.22  4021.4 1232.32  4117.3 1231.61    4120 1231.58  4222.4  1231.3
  4346.4 1228.71  4419.3 1225.83  4459.7  1224.8  4607.4 1221.97  4758.4 1217.73
  4791.9 1216.62  4881.5 1213.06  4886.7 1209.64  4922.1  1208.4  4927.2 1205.07
  4945.5 1206.04  4976.5  1204.6  4981.4 1203.26  4981.9 1202.76  4992.3 1203.26
  5017.3 1205.03  5027.7 1204.43  5033.1 1205.52  5062.6 1205.52  5081.3 1209.17
  5086.7 1211.72  5092.8 1213.12  5125.2  1214.9  5242.2 1218.13  5354.1 1218.84
#Mann= 11 ,-1 , 0
  3940.4     .05       0  4021.4     .12       0  4117.3     .05       0
    4120     .12       0  4419.3     .05       0  4459.7     .12       0
  4607.4     .05       0  4758.4     .12       0  4791.9     .05       0
  4981.4     .05       0  4992.3     .05       0
Bank Sta=4981.4,4992.3
XS Rating Curve= 0 ,0
Exp/Cntr=0.3,0.1

Type RM Length L Ch R = 1 ,9500    ,500,500,500
BEGIN DESCRIPTION:
LANG CREEK 19.0
END DESCRIPTION:
XS GIS Cut Line= 3
      2735152.96     10215490.34      2736270.62     10216356.17
      2736856.57     10216285.48
#Sta/Elev= 30
  3586.2  1229.7    4118 1211.67  4273.7 1210.84  4402.3 1214.24    4481 1213.36
  4644.9 1206.45  4665.7 1204.99  4673.9 1202.78  4694.7 1203.71  4709.2 1200.21
  4738.2 1201.04  4744.5 1199.93  4752.7 1202.62    4759 1201.65  4773.5 1205.32
  4837.8 1205.17  4937.3 1203.22  4951.8 1201.07  4958.2 1201.93  4966.3  1199.4
    4989 1197.09  4999.6 1194.79  5000.1 1194.29  5010.5 1194.79  5025.2 1195.48
  5055.5 1203.37  5068.9 1204.56  5186.4 1205.49  5509.3 1215.62  5590.2 1216.36
#Mann= 5 ,-1 , 0
  3586.2     .05       0    4989     .12       0  4999.6     .07       0
  5010.5     .12       0  5509.3     .05       0
Bank Sta=4999.6,5010.5
XS Rating Curve= 0 ,0
Exp/Cntr=0.3,0.1

Type RM Length L Ch R = 1 ,9000    ,500,500,500
BEGIN DESCRIPTION:
LANG CREEK 18.0
END DESCRIPTION:
XS GIS Cut Line= 3
      2735112.18     10215765.31       2736163.5     10216822.86
      2736660.33     10217191.24
#Sta/Elev= 30
  3508.8 1229.94  3863.3 1215.04  4139.1 1205.72  4181.5 1206.69  4358.3 1215.43
  4393.6 1216.11  4471.4 1215.81  4584.5 1210.92  4600.7 1208.65  4709.8 1199.38
    4726 1198.26  4754.2 1198.72  4761.3 1198.06  4768.4 1195.38  4775.4 1195.81
  4789.6  1199.7  4817.9 1200.58  4839.1 1196.69  4850.3 1196.59  4945.1  1197.1
  4980.5 1193.06  5002.1 1192.71  5002.6 1192.21  5015.7 1192.71  5044.3 1200.16
  5070.1  1202.4  5121.9 1205.57  5273.9 1212.26  5380.3 1214.21  5618.5    1222
#Mann= 8 ,-1 , 0
  3508.8     .05       0  4600.7     .12       0  4709.8     .05       0
  4850.3     .12       0  5002.1     .07       0  5015.7     .12       0
  5070.1     .12       0  5121.9     .05       0
Bank Sta=5002.1,5015.7
XS Rating Curve= 0 ,0
Exp/Cntr=0.3,0.1

Type RM Length L Ch R = 1 ,8500    ,500,500,500
BEGIN DESCRIPTION:
LANG CREEK 17.0
END DESCRIPTION:
XS GIS Cut Line= 3
      2734805.66     10216403.09      2735787.35     10217098.42
      2736205.65     10217503.08
#Sta/Elev= 30
    3797 1240.09    3861 1236.43  3919.6 1230.72  3991.3 1225.59    4027 1224.21
  4172.4 1217.39  4261.8 1212.93  4534.6 1201.44  4716.1 1191.15  4743.3 1193.79
  4793.8 1191.65  4801.9 1193.04  4900.9 1194.29  4924.3 1193.63  4966.1 1189.88
    4987 1188.68  4992.6 1186.99  4993.1 1186.49  5006.8 1186.99  5023.4 1189.87
  5058.7 1190.48  5094.2 1196.69  5157.7 1199.53  5164.7 1198.44  5221.3 1202.77
  5235.4 1202.37  5357.4 1208.33  5359.5 1208.49  5489.3 1215.34    5582 1220.61
#Mann= 12 ,-1 , 0
    3797     .05       0  3991.3     .12       0    4027     .05       0
  4172.4     .12       0  4261.8     .05       0  4534.6     .12       0
  4966.1     .05       0  4992.6     .03       0  5006.8     .05       0
  5357.4     .12       0  5359.5     .05       0  5489.3     .12       0
Bank Sta=4992.6,5006.8
XS Rating Curve= 0 ,0
Exp/Cntr=0.3,0.1

Type RM Length L Ch R = 1 ,8000    ,500,500,500
BEGIN DESCRIPTION:
LANG CREEK 16.0
END DESCRIPTION:
XS GIS Cut Line= 3
      2735155.69     10216853.14      2735363.85     10217340.22
      2735605.68     10217603.11
#Sta/Elev= 30
  4470.3  1207.2  4540.8 1203.76  4649.7 1199.03  4731.3 1194.49  4760.7 1191.49
  4789.7 1189.85  4796.5  1188.3  4807.4 1186.98  4818.8  1188.7  4850.9 1189.38
  4905.3 1187.54  4942.2 1189.56  4959.6 1188.56  4981.4 1184.05  4989.4 1183.17
  5017.5 1184.76  5031.4  1183.8  5031.7 1182.96  5032.2 1182.46  5045.4 1182.46
  5045.9 1182.96  5052.9 1186.96  5081.3 1189.36    5159 1192.45  5215.7 1195.51
  5236.7  1197.1  5247.9  1198.6  5307.6 1202.41  5329.1 1204.42  5357.2 1205.73
#Mann= 6 ,-1 , 0
  4470.3     .05       0  4540.8     .12       0  4649.7     .05       0
  5031.7     .03       0  5045.9     .05       0  5247.9     .12       0
Bank Sta=5031.7,5045.9
XS Rating Curve= 0 ,0
Exp/Cntr=0.3,0.1

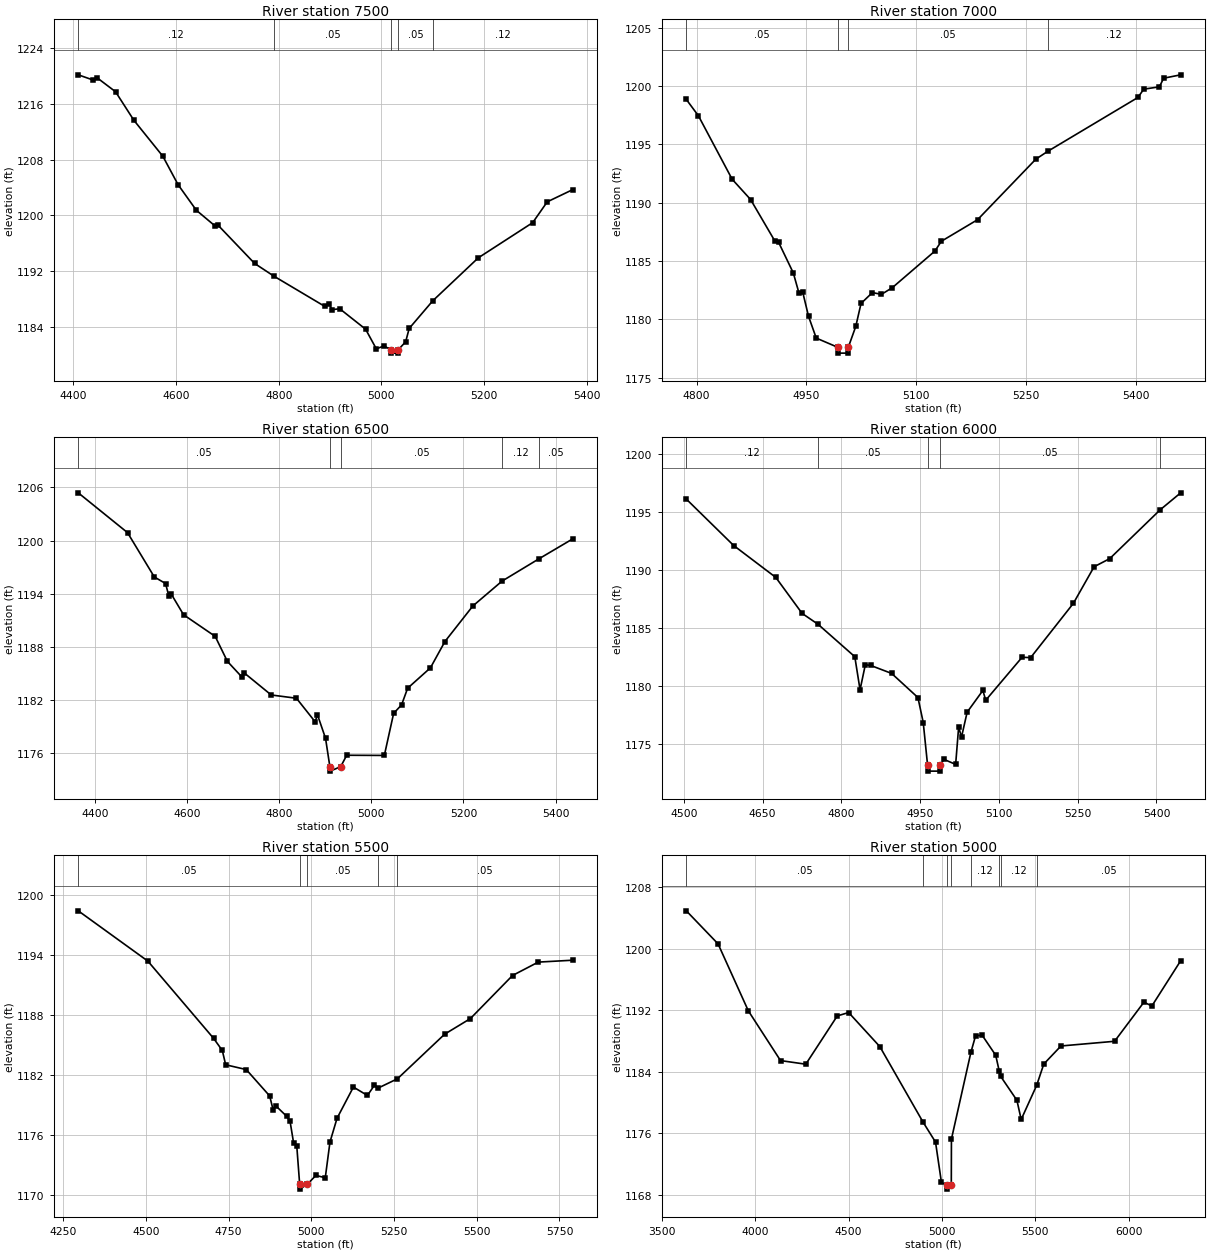
Type RM Length L Ch R = 1 ,7500    ,500,500,500
BEGIN DESCRIPTION:
LANG CREEK 15.0
END DESCRIPTION:
XS GIS Cut Line= 3
      2734455.67      10217253.1      2734937.11     10217595.02
       2735205.7     10217853.12
#Sta/Elev= 30
  4409.5 1220.19  4437.8 1219.46  4446.3 1219.76  4482.1 1217.76  4517.8 1213.66
  4574.3 1208.48  4603.9  1204.4  4639.5 1200.72  4675.2 1198.51  4681.3 1198.61
  4752.9 1193.08  4790.5 1191.25  4889.2 1186.92  4897.9 1187.23    4904 1186.43
  4918.8 1186.56  4969.2 1183.62  4990.1 1180.79  5004.7 1181.21  5018.6 1180.68
  5019.1 1180.18  5032.5 1180.18    5033 1180.68  5047.2 1181.81  5054.1 1183.73
    5100  1187.7  5188.7 1193.88  5294.7 1198.94    5323 1201.93  5372.5 1203.68
#Mann= 5 ,-1 , 0
  4409.5     .12       0  4790.5     .05       0  5018.6     .05       0
    5033     .05       0    5100     .12       0
Bank Sta=5018.6,5033
XS Rating Curve= 0 ,0
Exp/Cntr=0.3,0.1

Type RM Length L Ch R = 1 ,7000    ,500,500,500
BEGIN DESCRIPTION:
LANG CREEK 14.0
END DESCRIPTION:
XS GIS Cut Line= 3
       2734455.7     10217903.12      2734660.75     10217964.71
      2735055.68     10218203.11
#Sta/Elev= 30
  4785.9 1198.86  4802.4 1197.46  4848.5 1192.02  4873.7 1190.28  4906.7 1186.74
    4912 1186.61  4932.1 1183.98  4939.8 1182.26    4945 1182.32  4952.9 1180.26
  4963.4  1178.4  4992.8 1177.61  4993.3 1177.11  5006.7 1177.11  5007.2 1177.61
  5017.4  1179.4  5024.6 1181.37  5040.1  1182.3  5052.5 1182.15  5067.3 1182.72
  5125.5 1185.86  5134.3  1186.7  5183.8 1188.55  5263.4 1193.74  5279.9 1194.42
  5402.9 1199.03  5410.8 1199.74  5432.2 1199.94    5438 1200.68  5461.3 1200.97
#Mann= 4 ,-1 , 0
  4785.9     .05       0  4992.8     .03       0  5007.2     .05       0
  5279.9     .12       0
Bank Sta=4992.8,5007.2
XS Rating Curve= 0 ,0
Exp/Cntr=0.3,0.1

Type RM Length L Ch R = 1 ,6500    ,500,500,500
BEGIN DESCRIPTION:
LANG CREEK 13.0
END DESCRIPTION:
XS GIS Cut Line= 3
      2734348.28     10217843.07      2734547.93     10218447.65
      2734979.76     10218515.31
#Sta/Elev= 30
  4363.3 1205.38  4470.3 1200.89  4528.5 1195.89  4552.9 1195.15  4560.2 1193.71
  4565.5 1193.94    4592 1191.63  4660.7 1189.19  4687.2 1186.37    4719 1184.59
  4724.2 1185.05  4782.4 1182.58  4837.2 1182.21  4877.7 1179.56  4882.9 1180.34
  4900.4 1177.69  4909.8 1174.49  4910.3 1173.99  4933.2 1174.49  4946.4 1175.78
  5028.1 1175.76  5048.3 1180.51  5065.5 1181.46  5078.7 1183.34  5128.2 1185.64
  5159.7 1188.61  5220.4 1192.62  5283.7 1195.42    5364 1197.94  5437.1 1200.18
#Mann= 5 ,-1 , 0
  4363.3     .05       0  4909.8     .03       0  4933.2     .05       0
  5283.7     .12       0    5364     .05       0
Bank Sta=4909.8,4933.2
XS Rating Curve= 0 ,0
Exp/Cntr=0.3,0.1

Type RM Length L Ch R = 1 ,6000    ,500,500,500
BEGIN DESCRIPTION:
LANG CREEK 12.0
END DESCRIPTION:
XS GIS Cut Line= 3
      2733955.72     10218903.11       2734449.7     10218937.88
      2734855.73     10218753.09
#Sta/Elev= 30
  4504.8 1196.12    4595 1192.12  4675.2 1189.37  4725.3 1186.27  4755.7 1185.33
  4825.6 1182.54  4835.6 1179.69  4845.6 1181.84  4855.6 1181.79  4895.7  1181.1
  4945.8 1179.02  4955.9 1176.87  4964.2 1173.18  4964.7 1172.68  4987.1 1172.68
  4987.6 1173.18  4995.5 1173.69  5017.6 1173.26  5023.3 1176.47  5028.8 1175.62
  5039.5 1177.76  5069.4 1179.63  5074.9 1178.79  5144.1 1182.49  5160.4 1182.46
  5241.8 1187.14  5281.2 1190.29    5311 1190.99  5407.1  1195.2  5446.1 1196.66
#Mann= 5 ,-1 , 0
  4504.8     .12       0  4755.7     .05       0  4964.2     .03       0
  4987.6     .05       0  5407.1     .12       0
Bank Sta=4964.2,4987.6
XS Rating Curve= 0 ,0
Exp/Cntr=0.3,0.1

Type RM Length L Ch R = 1 ,5500    ,500,500,500
BEGIN DESCRIPTION:
LANG CREEK 11.0
END DESCRIPTION:
XS GIS Cut Line= 3
      2733900.11     10219544.03      2734588.55     10219395.88
      2735161.92     10218852.56
#Sta/Elev= 30
  4295.8 1198.38  4506.1 1193.35  4704.9 1185.62  4731.1 1184.41  4741.3 1182.98
  4803.5  1182.5  4874.3 1179.86  4884.5 1178.49    4892  1178.9  4925.5 1177.83
  4935.7 1177.36  4946.4  1175.2  4956.1 1174.89  4964.9 1171.04  4965.4 1170.54
  4988.4 1171.04    5014 1171.91  5042.3 1171.68  5056.5 1175.25  5077.9 1177.63
  5127.3 1180.75  5169.7 1179.91  5190.8 1180.93  5202.1 1180.65  5260.5 1181.58
  5403.1 1186.04  5480.8  1187.6  5608.2 1191.91  5685.9 1193.25  5789.9 1193.44
#Mann= 5 ,-1 , 0
  4295.8     .05       0  4964.9     .03       0  4988.4     .05       0
  5202.1     .12       0  5260.5     .05       0
Bank Sta=4964.9,4988.4
XS Rating Curve= 0 ,0
Exp/Cntr=0.3,0.1

Type RM Length L Ch R = 1 ,5000    ,500,500,500
BEGIN DESCRIPTION:
LANG CREEK 10.0
END DESCRIPTION:
XS GIS Cut Line= 4
      2733777.89      10219757.9      2734674.22      10219900.5
      2735035.08     10219614.58      2736059.44      10218851.4
#Sta/Elev= 30
    3632 1204.91  3801.9 1200.61  3963.9  1191.9  4136.1 1185.43  4271.3 1184.96
  4439.8 1191.24  4500.6 1191.68  4667.5 1187.25  4897.9 1177.46  4965.5 1174.83
  4997.2 1169.58  5026.4 1169.21  5026.9 1168.71  5049.9 1169.21  5050.6 1175.21
  5154.9 1186.51  5179.9 1188.67  5215.3 1188.72  5287.6 1186.12  5306.7 1184.03
    5314 1183.38  5400.9 1180.27  5423.9 1177.77  5506.7 1182.21  5544.8 1184.98
  5636.7 1187.33  5923.6 1187.94  6080.7 1193.03  6123.1 1192.53  6277.4 1198.42
#Mann= 8 ,-1 , 0
    3632     .05       0  4897.9     .12       0  5026.4     .07       0
  5049.9     .12       0  5154.9     .12       0  5306.7     .05       0
    5314     .12       0  5506.7     .05       0
Bank Sta=5026.4,5049.9
XS Rating Curve= 0 ,0
Exp/Cntr=0.3,0.1