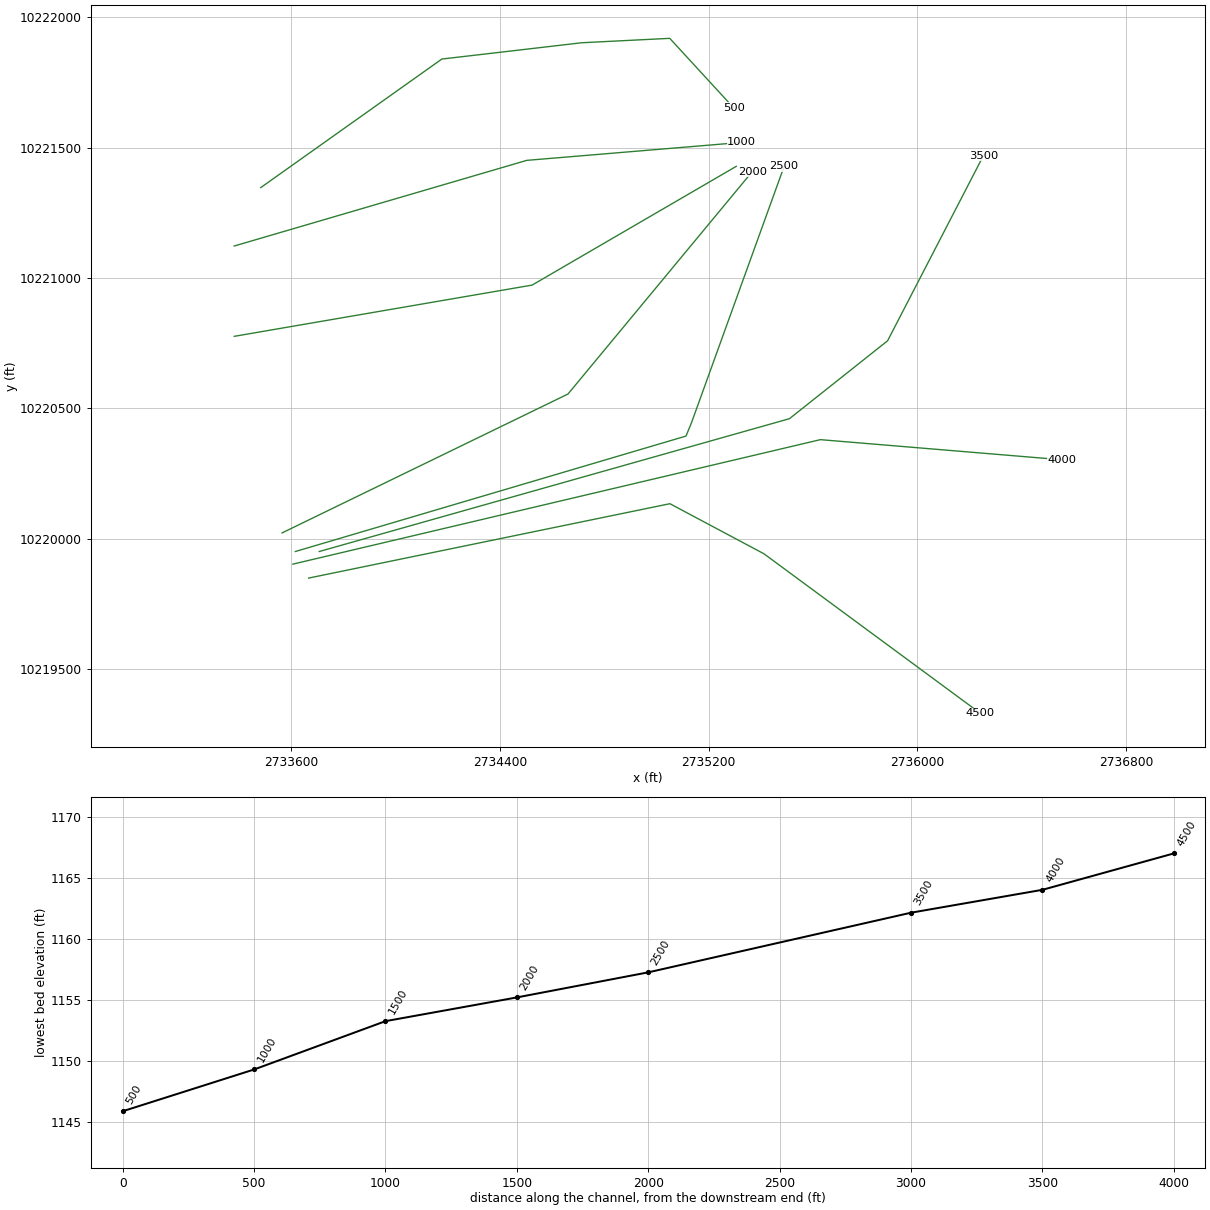
HEC-RAS study LANG CREEK.prj: LANG CREEK Base Level Engineering

--- LANG CREEK.g01 (geometry) --- (continued)

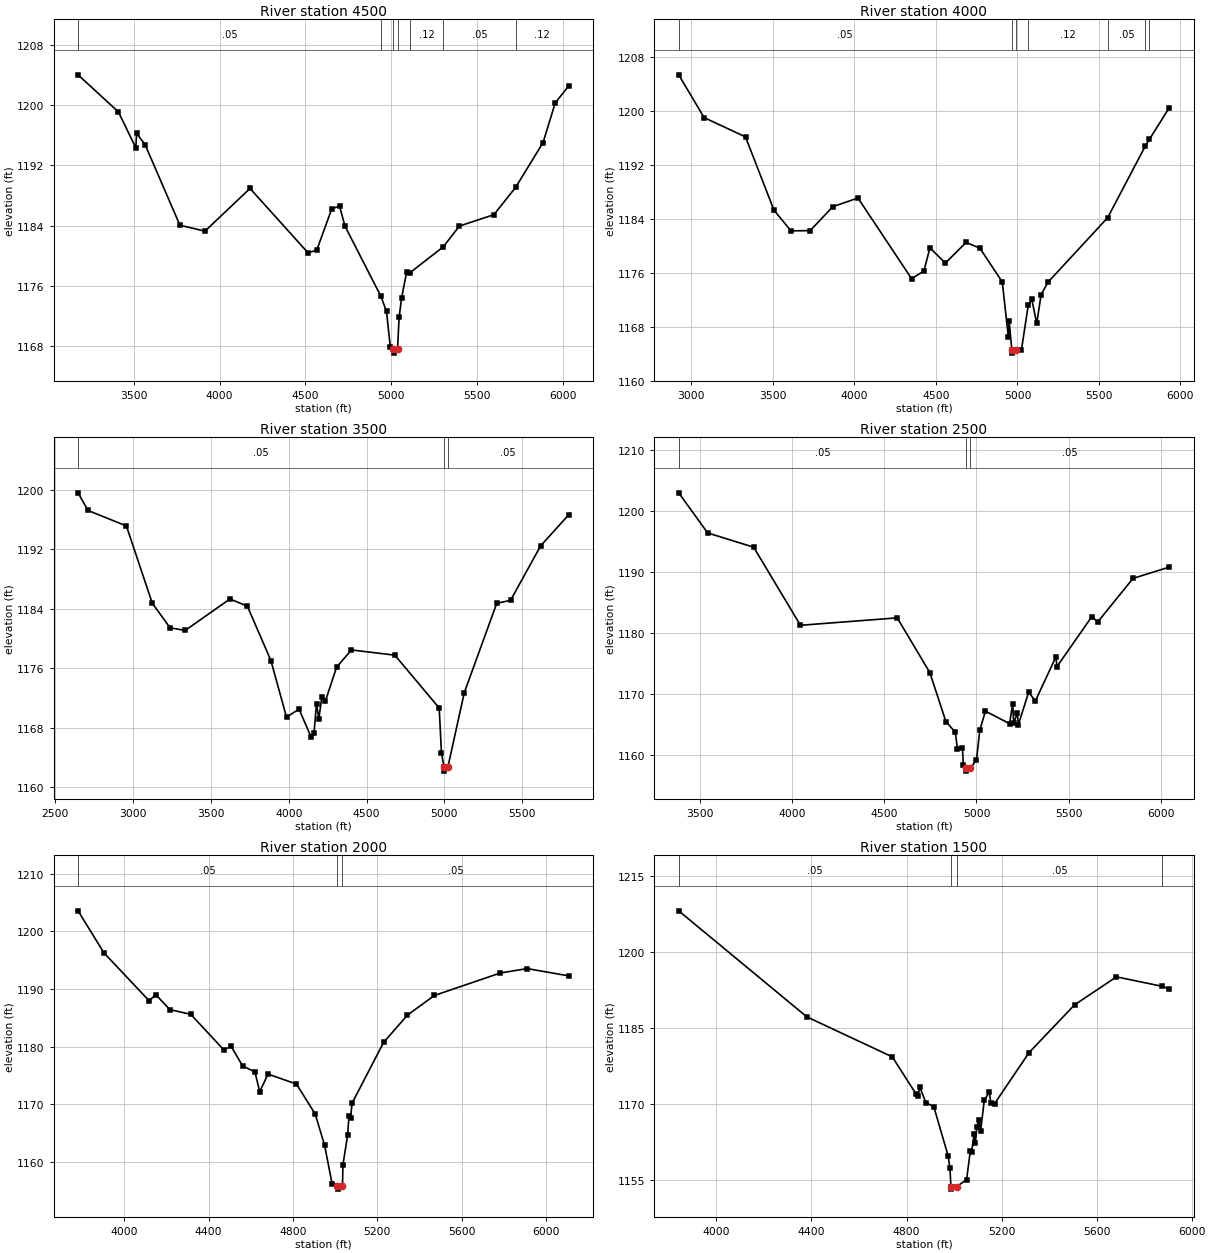
Type RM Length L Ch R = 1 ,4500    ,500,500,500
BEGIN DESCRIPTION:
LANG CREEK 9.0
END DESCRIPTION:
XS GIS Cut Line= 4
      2733665.85     10219849.57      2735051.07     10220134.76
      2735411.82     10219942.63      2736241.72     10219330.88
#Sta/Elev= 30
    3177 1204.04  3411.7 1199.11  3512.8 1194.35  3517.9 1196.27  3568.2  1194.7
  3769.5 1184.05  3915.3 1183.26  4177.4 1188.94  4514.3  1180.4  4565.4 1180.72
  4653.4 1186.25  4698.5 1186.58  4729.9 1183.93  4938.1 1174.64  4971.6  1172.6
  4993.5  1167.9  5012.1 1167.55  5012.6 1167.05  5035.8 1167.55  5044.8 1171.79
  5059.4  1174.4  5088.7 1177.81  5106.4 1177.71  5301.5 1181.17  5395.7 1183.94
  5596.2 1185.45  5722.4 1189.07  5882.3 1195.03  5953.3 1200.31    6031 1202.55
#Mann= 7 ,-1 , 0
    3177     .05       0  4938.1     .12       0  5012.1     .07       0
  5035.8     .12       0  5106.4     .12       0  5301.5     .05       0
  5722.4     .12       0
Bank Sta=5012.1,5035.8
XS Rating Curve= 0 ,0
Exp/Cntr=0.3,0.1

Type RM Length L Ch R = 1 ,4000    ,500,500,500
BEGIN DESCRIPTION:
LANG CREEK 8.0
END DESCRIPTION:
XS GIS Cut Line= 3
      2733605.65      10219903.1      2735627.91     10220380.32
       2736555.7     10220303.11
#Sta/Elev= 30
  2922.2  1205.3  3078.1 1198.96    3332  1196.1  3506.4 1185.25  3610.6 1182.18
  3728.3 1182.21  3867.5 1185.76  4021.6 1187.05  4350.4  1175.1  4425.9 1176.21
  4463.1 1179.66    4558  1177.4    4685 1180.47  4769.6 1179.61  4906.9 1174.61
    4944 1166.49  4949.2 1168.78  4965.3 1164.56  4965.8 1164.06    4989 1164.56
  5024.7 1164.58  5066.1 1171.15  5088.1 1172.01  5118.2 1168.47  5145.2 1172.73
  5188.4  1174.6  5553.2 1184.13  5785.2 1194.78  5809.5 1195.74    5931 1200.42
#Mann= 7 ,-1 , 0
  2922.2     .05       0  4965.3     .03       0    4989     .05       0
  5066.1     .12       0  5553.2     .05       0  5785.2     .12       0
  5809.5     .05       0
Bank Sta=4965.3,4989
XS Rating Curve= 0 ,0
Exp/Cntr=0.3,0.1

Type RM Length L Ch R = 1 ,3500    ,1000,1000,1000
BEGIN DESCRIPTION:
LANG CREEK 7.0
END DESCRIPTION:
XS GIS Cut Line= 4
      2733706.66     10219951.44      2735509.41     10220460.69
      2735885.74     10220759.46      2736252.68     10221468.54
#Sta/Elev= 30
  2646.2 1199.57  2710.1  1197.2  2956.9 1195.12  3123.2 1184.73  3237.5 1181.44
  3334.5 1181.08    3622 1185.31  3734.3 1184.34  3885.8 1177.01  3985.7 1169.42
  4066.1 1170.52  4144.4 1166.72  4162.3 1167.29  4178.4 1171.22  4193.5 1169.21
  4212.4 1172.14  4235.1 1171.56  4307.8 1176.16  4403.1 1178.46  4681.6 1177.76
  4966.8 1170.66  4981.3 1164.68  4998.4 1162.68  4998.9 1162.18  5022.2 1162.68
    5128 1172.71  5336.7 1184.73  5425.3 1185.12  5618.9 1192.45  5798.4  1196.6
#Mann= 3 ,-1 , 0
  2646.2     .05       0  4998.4     .03       0  5022.2     .05       0
Bank Sta=4998.4,5022.2
XS Rating Curve= 0 ,0
Exp/Cntr=0.3,0.1

Type RM Length L Ch R = 1 ,2500    ,500,500,500
BEGIN DESCRIPTION:
LANG CREEK 5.0
END DESCRIPTION:
XS GIS Cut Line= 4
      2733614.94     10219951.42      2735112.78     10220394.05
       2735133.5     10220444.38      2735489.01     10221428.22
#Sta/Elev= 30
  3383.7 1203.02  3540.9 1196.43  3790.7 1194.08  4044.5 1181.25  4569.9 1182.47
  4746.7 1173.48  4833.9 1165.43  4885.1 1163.67  4896.5 1160.89  4923.6 1161.16
  4928.8 1158.25  4943.4 1157.78  4943.9 1157.28  4967.3 1157.78    5000 1159.14
  5017.9 1164.01  5048.5 1167.14  5179.4 1165.08  5196.5 1168.34  5201.8 1165.21
  5221.9 1166.79  5227.2 1164.91  5283.2 1170.27  5319.2 1168.79  5431.2 1176.07
  5436.5 1174.45    5626 1182.67  5657.9 1181.79  5849.8 1188.96  6046.1 1190.81
#Mann= 3 ,-1 , 0
  3383.7     .05       0  4943.4     .05       0  4967.3     .05       0
Bank Sta=4943.4,4967.3
XS Rating Curve= 0 ,0
Exp/Cntr=0.3,0.1

Type RM Length L Ch R = 1 ,2000    ,500,500,500
BEGIN DESCRIPTION:
LANG CREEK 4.0
END DESCRIPTION:
XS GIS Cut Line= 3
      2733564.06     10220022.73      2734660.35     10220555.28
      2735366.83     10221407.93
#Sta/Elev= 30
  3781.2 1203.58  3903.8 1196.28    4118 1187.96  4149.9 1189.01  4216.6 1186.41
  4315.5  1185.6  4472.3 1179.42  4507.1 1180.04  4561.2 1176.64  4619.9 1175.58
  4642.5 1172.16    4682 1175.21  4816.9 1173.48  4905.9 1168.25  4950.3 1162.83
  4986.4 1156.03  5011.2 1155.72  5011.7 1155.22  5035.1 1155.72  5037.3 1159.46
  5059.4 1164.59  5065.9 1167.96  5073.7 1167.62  5080.2 1170.13    5230 1180.71
  5343.3 1185.47    5471 1188.87  5783.5 1192.78  5911.2 1193.54  6107.3 1192.28
#Mann= 3 ,-1 , 0
  3781.2     .05       0  5011.2     .05       0  5035.1     .05       0
Bank Sta=5011.2,5035.1
XS Rating Curve= 0 ,0
Exp/Cntr=0.3,0.1

Type RM Length L Ch R = 1 ,1500    ,500,500,500
BEGIN DESCRIPTION:
LANG CREEK 3.0
END DESCRIPTION:
XS GIS Cut Line= 3
      2733380.75     10220776.44      2734522.77     10220972.88
      2735305.58     10221428.21
#Sta/Elev= 30
  3841.2  1208.1  4380.4 1187.21  4740.1 1179.33  4840.6 1171.97  4849.8 1171.59
  4854.8 1173.47  4881.2 1170.33  4914.8 1169.51  4974.7 1159.89  4982.7 1157.35
  4986.9 1153.77  4987.4 1153.27  5010.9 1153.77  5052.8 1155.13  5068.5 1160.85
  5074.3 1160.67  5084.3 1164.13    5090 1162.32  5095.9 1165.59  5105.8 1166.89
  5111.6 1164.67  5127.3 1170.81  5148.8 1172.39  5154.6 1170.17  5170.3  1170.1
  5315.7 1180.17  5507.1 1189.57  5683.4 1195.09  5876.8 1193.22  5905.6 1192.69
#Mann= 4 ,-1 , 0
  3841.2     .05       0  4986.9     .03       0  5010.9     .05       0
  5876.8     .05       0
Bank Sta=4986.9,5010.9
XS Rating Curve= 0 ,0
Exp/Cntr=0.3,0.1

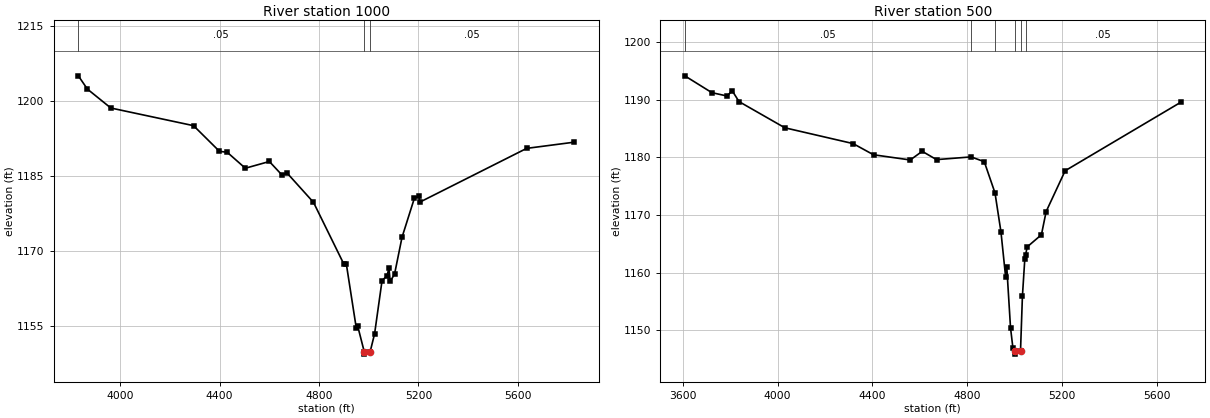
Type RM Length L Ch R = 1 ,1000    ,500,500,500
BEGIN DESCRIPTION:
LANG CREEK 2.0
END DESCRIPTION:
XS GIS Cut Line= 3
      2733380.68     10221122.72      2734502.39     10221451.13
      2735326.12     10221519.95
#Sta/Elev= 30
  3831.2 1205.08  3867.7 1202.42  3961.9 1198.63  4294.9 1195.09  4399.1 1189.95
  4430.3 1189.76  4503.3 1186.56    4600 1187.91  4649.2 1185.28  4672.1 1185.55
  4777.6 1179.72  4899.2  1167.4  4909.7 1167.38  4949.9 1154.48  4955.1    1155
  4981.7  1149.8  4982.2  1149.3  5005.7  1149.8  5023.4 1153.36  5053.5 1164.05
  5073.5 1164.99  5081.2 1166.54  5086.2  1163.9  5103.7 1165.31  5133.8 1172.71
  5183.9  1180.6  5201.5 1180.93  5206.5 1179.79  5635.5 1190.54  5826.6 1191.78
#Mann= 3 ,-1 , 0
  3831.2     .05       0  4981.7     .05       0  5005.7     .05       0
Bank Sta=4981.7,5005.7
XS Rating Curve= 0 ,0
Exp/Cntr=0.3,0.1

Type RM Length L Ch R = 1 ,500     ,0,0,0
BEGIN DESCRIPTION:
LANG CREEK 1.0
END DESCRIPTION:
XS GIS Cut Line= 5
      2733482.59     10221346.82      2734176.69     10221839.53
      2734712.96     10221902.01      2735050.38     10221918.95
      2735295.51     10221652.36
#Sta/Elev= 30
  3608.9 1194.13  3723.1 1191.21  3787.2 1190.63  3808.9 1191.54  3837.6 1189.66
  4030.8 1185.12  4318.6 1182.38  4404.8 1180.44  4559.8 1179.54  4610.1 1181.04
  4670.5  1179.6  4816.5 1180.07  4871.9 1179.24  4917.1 1173.83  4942.3 1167.06
  4961.9 1159.27  4966.9 1160.92  4982.6 1150.45  4992.7 1146.92  5000.7 1146.37
  5001.2 1145.87  5024.7 1146.37  5032.8 1155.94  5042.8 1162.34  5046.2 1163.06
  5052.8 1164.46  5112.9 1166.57  5132.9  1170.6    5213 1177.67    5700 1189.53
#Mann= 6 ,-1 , 0
  3608.9     .05       0  4816.5     .05       0  4917.1     .12       0
  5000.7     .07       0  5024.7     .12       0  5046.2     .05       0
Bank Sta=5000.7,5024.7
XS Rating Curve= 0 ,0
Exp/Cntr=0.3,0.1
Stream Node=LANG CREEK      ,Reach-1         , 0 , 0 ,Upstream end
Stream Node=LANG CREEK      ,Reach-1         , 0 , 1 ,Downstream end

Chan Stop Cuts=-1
Use User Specified Reach Order=0
Composite Channel Slope=5