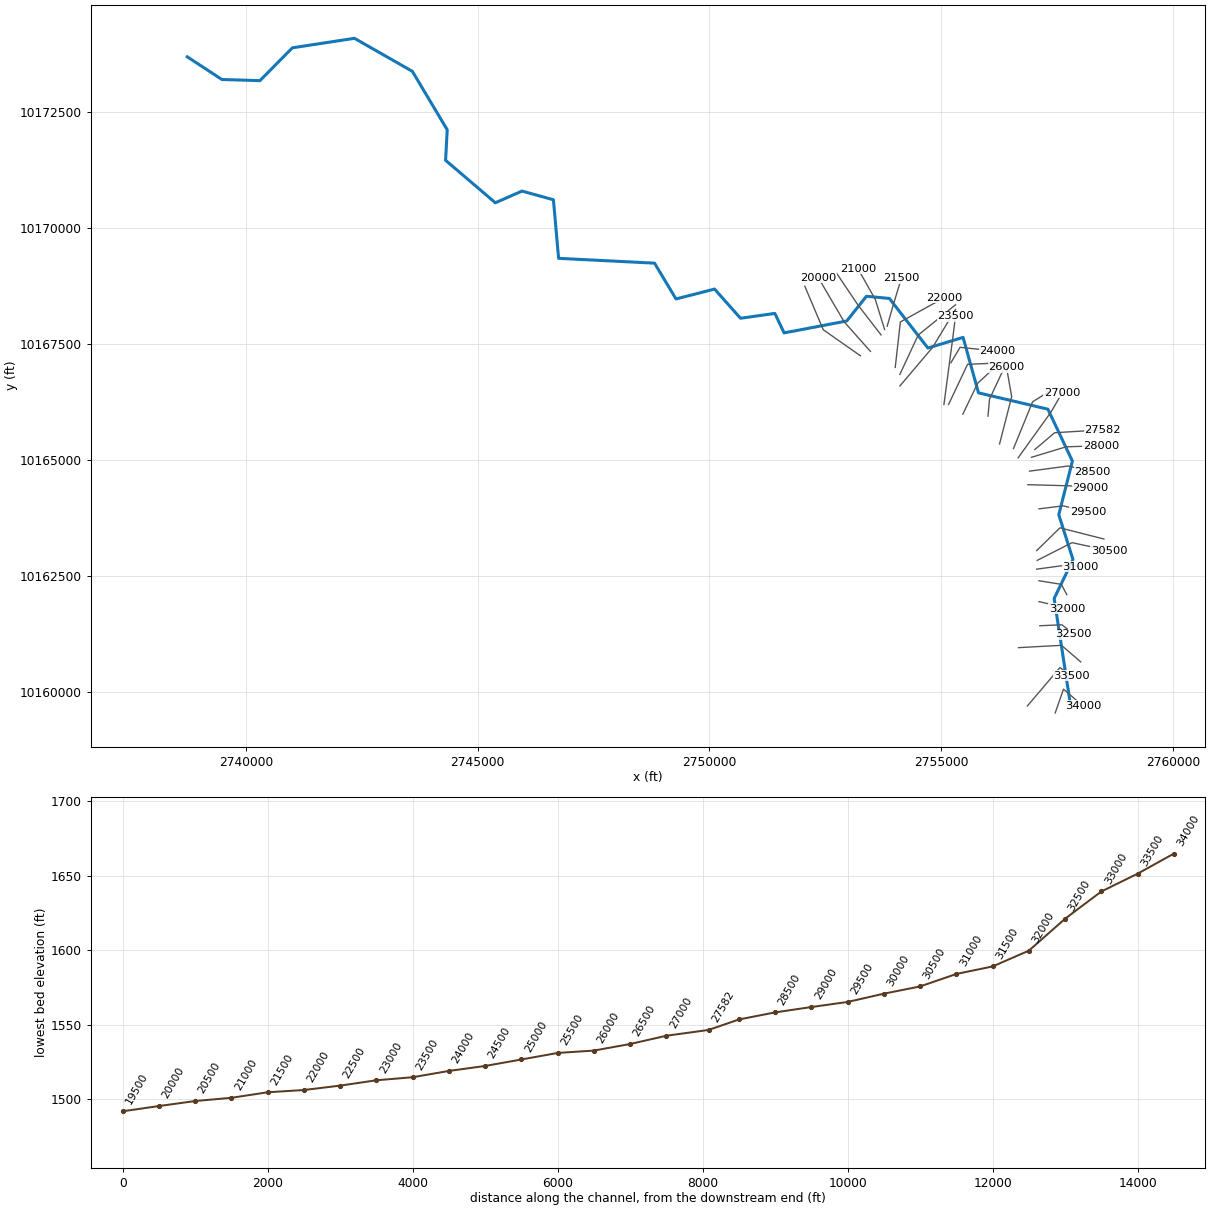
--- LEFT HAND CREEK.prj (project) ---

Proj Title=LEFT HAND CREEK Base Level Engineering
Current Plan=p01
Default Exp/Contr=0.3,0.1
English Units
Geom File=g01
Flow File=f01
Plan File=p01
BEGIN DESCRIPTION:
LEFT HAND CREEK
END DESCRIPTION:

--- LEFT HAND CREEK.p01 (plan) ---

Plan Title=Multiple Run
Short Identifier=Multiple
Geom File=g01
Flow File=f01
Subcritical Flow
K Sum by GR= 0
Std Step Tol= 0.01
Critical Tol= 0.01
Num of Std Step Trials= 20
Max Error Tol= 0.3
Flow Tol Ratio= 0.001
Split Flow NTrial= 30
Split Flow Tol= 0.02
Split Flow Ratio= 0.02
Log Output Level= 0
Friction Slope Method= 1
Unsteady Friction Slope Method= 2
Unsteady Bridges Friction Slope Method= 1
Parabolic Critical Depth
Global Vel Dist=  1 , 1 , 1
Global Log Level= 0
CheckData=True
Encroach Param= -1, 0, 0, 0
BEGIN DESCRIPTION:
Multiple Run
END DESCRIPTION:

--- LEFT HAND CREEK.f01 (steady flow) ---

Flow Title=Multiple
Number of Profiles=7
Profile Names=10-year,25-year,50-year,1pct_min,100-year,1pct_plu,500-year
River Rch & RM= LEFT HAND CREEK,Reach-1,34000
     489     800    1288     965    1766    3233    2495
River Rch & RM= LEFT HAND CREEK,Reach-1,25500
     703    1179    1871    1352    2588    4955    3635
River Rch & RM= LEFT HAND CREEK,Reach-1,21000
     842    1427    2301    1651    3204    6215    4491
River Rch & RM= LEFT HAND CREEK,Reach-1,19000
     992    1693    2862    2082    4013    7734    5614
River Rch & RM= LEFT HAND CREEK,Reach-1,18500
    1067    1832    3053    2188    4287    8400    5994
River Rch & RM= LEFT HAND CREEK,Reach-1,16500
    1354    2353    4085    2951    5786   11341    8057
River Rch & RM= LEFT HAND CREEK,Reach-1,14500
    1532    2691    4746    3370    6771   13605    9467
River Rch & RM= LEFT HAND CREEK,Reach-1,10500
    1638    2888    5129    3628    7337   14838   10258
River Rch & RM= LEFT HAND CREEK,Reach-1,9000
    1853    3297    5880    4115    8451   17355   11815
River Rch & RM= LEFT HAND CREEK,Reach-1,5500
    1886    3361    5946    4140    8544   17633   11940
River Rch & RM= LEFT HAND CREEK,Reach-1,5000
    2254    4066    7149    4911   10317   21674   14374
Boundary for River Rch & Prof#=LEFT HAND CREEK,Reach-1,1
Up Type=0
Dn Type=3
Dn Slope=0.005
Boundary for River Rch & Prof#=LEFT HAND CREEK,Reach-1,2
Up Type=0
Dn Type=3
Dn Slope=0.005
Boundary for River Rch & Prof#=LEFT HAND CREEK,Reach-1,3
Up Type=0
Dn Type=3
Dn Slope=0.005
Boundary for River Rch & Prof#=LEFT HAND CREEK,Reach-1,4
Up Type=0
Dn Type=3
Dn Slope=0.005
Boundary for River Rch & Prof#=LEFT HAND CREEK,Reach-1,5
Up Type=0
Dn Type=3
Dn Slope=0.005
Boundary for River Rch & Prof#=LEFT HAND CREEK,Reach-1,6
Up Type=0
Dn Type=3
Dn Slope=0.005
Boundary for River Rch & Prof#=LEFT HAND CREEK,Reach-1,7
Up Type=0
Dn Type=3
Dn Slope=0.005

--- LEFT HAND CREEK.g01 (geometry) ---

Geom Title=Existing Conditions

River Reach=LEFT HAND CREEK,Reach-1
Reach XY= 30
      2757784.50     10159730.00      2757433.00     10162020.00
      2757839.00     10162861.00      2757532.75     10163827.00
      2757826.50     10164983.00      2757297.75     10166102.00
      2755802.00     10166454.00      2755468.75     10167650.00
      2754710.50     10167421.00      2753879.25     10168490.00
      2753384.75     10168537.00      2752960.50     10168004.00
      2751609.00     10167747.00      2751410.00     10168167.00
      2750668.50     10168063.00      2750109.00     10168692.00
      2749277.50     10168479.00      2748814.50     10169251.00
      2746745.75     10169355.00      2746634.50     10170618.00
      2745956.50     10170805.00      2745382.00     10170553.00
      2744308.50     10171469.00      2744344.00     10172127.00
      2743592.00     10173387.00      2742343.75     10174099.00
      2741004.25     10173894.00      2740305.25     10173186.00
      2739484.75     10173211.00      2738738.25     10173700.00

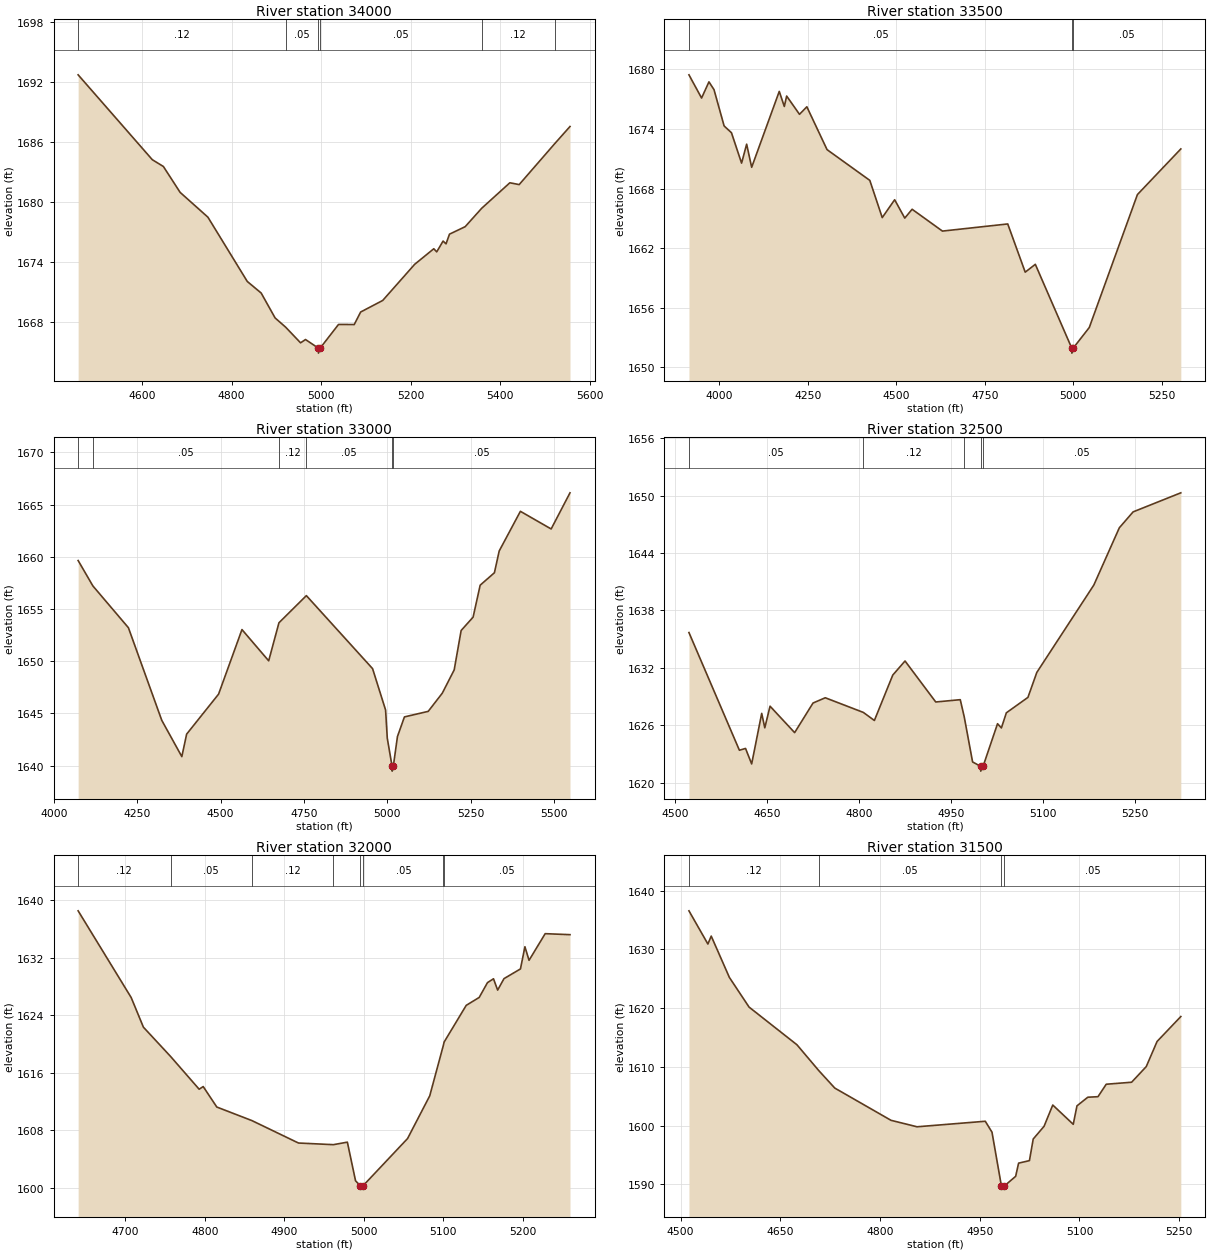
Type RM Length L Ch R = 1,34000,500,500,500
BEGIN DESCRIPTION:
LEFT HAND CREEK 68.0
END DESCRIPTION:
XS GIS Cut Line= 3
      2757455.67     10159553.08      2757634.20     10160066.11
      2758055.72     10159703.08
#Sta/Elev= 30
  4456.8 1692.71  4622.6 1684.22  4647.4 1683.54  4684.8 1680.95  4746.9 1678.47
  4834.9 1672.04  4866.0 1670.88  4897.1 1668.39  4920.6 1667.47  4954.0 1665.90
  4965.1 1666.23  4993.8 1665.37  4994.0 1664.87  4997.8 1665.37  5038.9 1667.74
  5074.0 1667.73  5088.3 1668.98  5137.7 1670.14  5209.0 1673.75  5251.8 1675.31
  5258.4 1675.00  5272.6 1676.08  5279.2 1675.80  5286.9 1676.77  5322.0 1677.52
  5358.7 1679.35  5421.8 1681.91  5442.7 1681.73  5521.7 1685.80  5556.3 1687.54
#Mann=6,-1,0
  4456.8    0.12       0  4920.6    0.05       0  4993.8    0.05       0
  4997.8    0.05       0  5358.7    0.12       0  5521.7    0.05       0
Bank Sta=4993.8,4997.8
Exp/Cntr=0.3,0.1

Type RM Length L Ch R = 1,33500,500,500,500
BEGIN DESCRIPTION:
LEFT HAND CREEK 67.0
END DESCRIPTION:
XS GIS Cut Line= 3
      2756855.71     10159703.14      2757558.71     10160531.03
      2757805.70     10160353.10
#Sta/Elev= 30
  3913.9 1679.46  3949.6 1677.12  3970.4 1678.75  3984.7 1677.97  4013.3 1674.31
  4034.1 1673.62  4062.7 1670.56  4077.0 1672.47  4091.2 1670.14  4169.2 1677.79
  4183.5 1676.27  4190.1 1677.32  4226.4 1675.48  4247.2 1676.24  4304.3 1671.92
  4425.2 1668.82  4460.3 1665.07  4495.4 1666.87  4524.0 1665.02  4544.8 1665.91
  4630.5 1663.71  4815.1 1664.43  4864.5 1659.57  4893.1 1660.36  4996.1 1651.91
  4996.3 1651.41  5000.1 1651.91  5045.6 1653.99  5181.7 1667.39  5304.4 1671.99
#Mann=3,-1,0
  3913.9    0.05       0  4996.1    0.05       0  5000.1    0.05       0
Bank Sta=4996.1,5000.1
Exp/Cntr=0.3,0.1

Type RM Length L Ch R = 1,33000,500,500,500
BEGIN DESCRIPTION:
LEFT HAND CREEK 66.0
END DESCRIPTION:
XS GIS Cut Line= 3
      2756665.22     10160960.54      2757590.86     10161010.72
      2758005.69     10160653.11
#Sta/Elev= 30
  4073.0 1659.64  4117.2 1657.21  4223.7 1653.21  4323.8 1644.34  4383.9 1640.87
  4398.3 1643.02  4494.1 1646.85  4564.2 1653.03  4644.3 1650.04  4675.1 1653.68
  4757.3 1656.28  4955.8 1649.29  4994.8 1645.33  4999.9 1642.63  5014.1 1639.98
  5014.4 1639.48  5018.1 1639.98  5030.4 1642.79  5051.3 1644.67  5122.6 1645.20
  5164.8 1646.94  5200.5 1649.17  5221.3 1652.94  5257.2 1654.22  5278.4 1657.28
  5321.1 1658.47  5335.4 1660.55  5399.0 1664.35  5491.2 1662.66  5547.7 1666.12
#Mann=6,-1,0
  4073.0    0.12       0  4117.2    0.05       0  4675.1    0.12       0
  4757.3    0.05       0  5014.1    0.05       0  5018.1    0.05       0
Bank Sta=5014.1,5018.1
Exp/Cntr=0.3,0.1

Type RM Length L Ch R = 1,32500,500,500,500
BEGIN DESCRIPTION:
LEFT HAND CREEK 65.0
END DESCRIPTION:
XS GIS Cut Line= 3
      2757123.49     10161432.76      2757600.92     10161454.04
      2757855.71     10161253.09
#Sta/Elev= 30
  4522.1 1635.69  4604.4 1623.40  4614.4 1623.59  4624.4 1621.97  4640.8 1627.25
  4645.8 1625.74  4654.4 1628.00  4694.5 1625.24  4724.5 1628.33  4744.5 1628.88
  4806.6 1627.35  4824.6 1626.51  4854.6 1631.25  4874.6 1632.72  4924.7 1628.44
  4964.7 1628.68  4971.1 1626.91  4984.8 1622.18  4997.9 1621.72  4998.1 1621.22
  5001.9 1621.72  5025.5 1626.17  5031.8 1625.73  5039.9 1627.31  5075.1 1628.92
  5089.6 1631.53  5182.6 1640.65  5224.2 1646.63  5246.7 1648.29  5324.5 1650.28
#Mann=5,-1,0
  4522.1    0.05       0  4806.6    0.12       0  4971.1    0.05       0
  4997.9    0.05       0  5001.9    0.05       0
Bank Sta=4997.9,5001.9
Exp/Cntr=0.3,0.1

Type RM Length L Ch R = 1,32000,500,500,500
BEGIN DESCRIPTION:
LEFT HAND CREEK 64.0
END DESCRIPTION:
XS GIS Cut Line= 3
      2757105.72     10161953.10      2757455.71     10161872.30
      2757705.71     10161803.10
#Sta/Elev= 30
  4640.8 1638.55  4707.5 1626.48  4722.9 1622.35  4757.1 1618.27  4793.0 1613.71
  4798.1 1614.08  4815.2 1611.23  4859.4 1609.34  4917.9 1606.22  4961.8 1605.99
  4979.4 1606.34  4989.7 1600.96  4995.4 1600.30  4995.7 1599.80  4999.4 1600.30
  5055.1 1606.84  5083.0 1612.79  5100.2 1619.85  5101.1 1620.28  5128.9 1625.39
  5145.2 1626.49  5155.6 1628.55  5163.2 1629.09  5168.4 1627.51  5176.4 1629.11
  5197.1 1630.46  5202.7 1633.55  5207.9 1631.66  5228.2 1635.37  5259.4 1635.23
#Mann=8,-1,0
  4640.8    0.12       0  4757.1    0.05       0  4859.4    0.12       0
  4961.8    0.05       0  4995.4    0.05       0  4999.4    0.05       0
  5100.2    0.12       0  5101.1    0.05       0
Bank Sta=4995.4,4999.4
Exp/Cntr=0.3,0.1

Type RM Length L Ch R = 1,31500,500,500,500
BEGIN DESCRIPTION:
LEFT HAND CREEK 63.0
END DESCRIPTION:
XS GIS Cut Line= 3
      2757105.66     10162403.12      2757586.89     10162325.84
      2757705.67     10162103.14
#Sta/Elev= 30
  4512.6 1636.57  4541.1 1630.92  4546.1 1632.27  4573.4 1625.24  4603.0 1620.19
  4675.0 1613.78  4707.8 1609.39  4731.9 1606.41  4816.5 1600.92  4855.7 1599.82
  4958.3 1600.76  4968.4 1598.90  4982.6 1589.71  4982.9 1589.21  4986.6 1589.71
  5004.0 1591.39  5008.4 1593.63  5024.7 1594.06  5030.4 1597.74  5046.7 1599.90
  5059.8 1603.52  5090.6 1600.24  5096.2 1603.38  5112.5 1604.85  5127.8 1604.94
  5140.2 1607.06  5178.4 1607.40  5200.4 1610.06  5216.7 1614.34  5252.4 1618.58
#Mann=4,-1,0
  4512.6    0.12       0  4707.8    0.05       0  4982.6    0.05       0
  4986.6    0.05       0
Bank Sta=4982.6,4986.6
Exp/Cntr=0.3,0.1

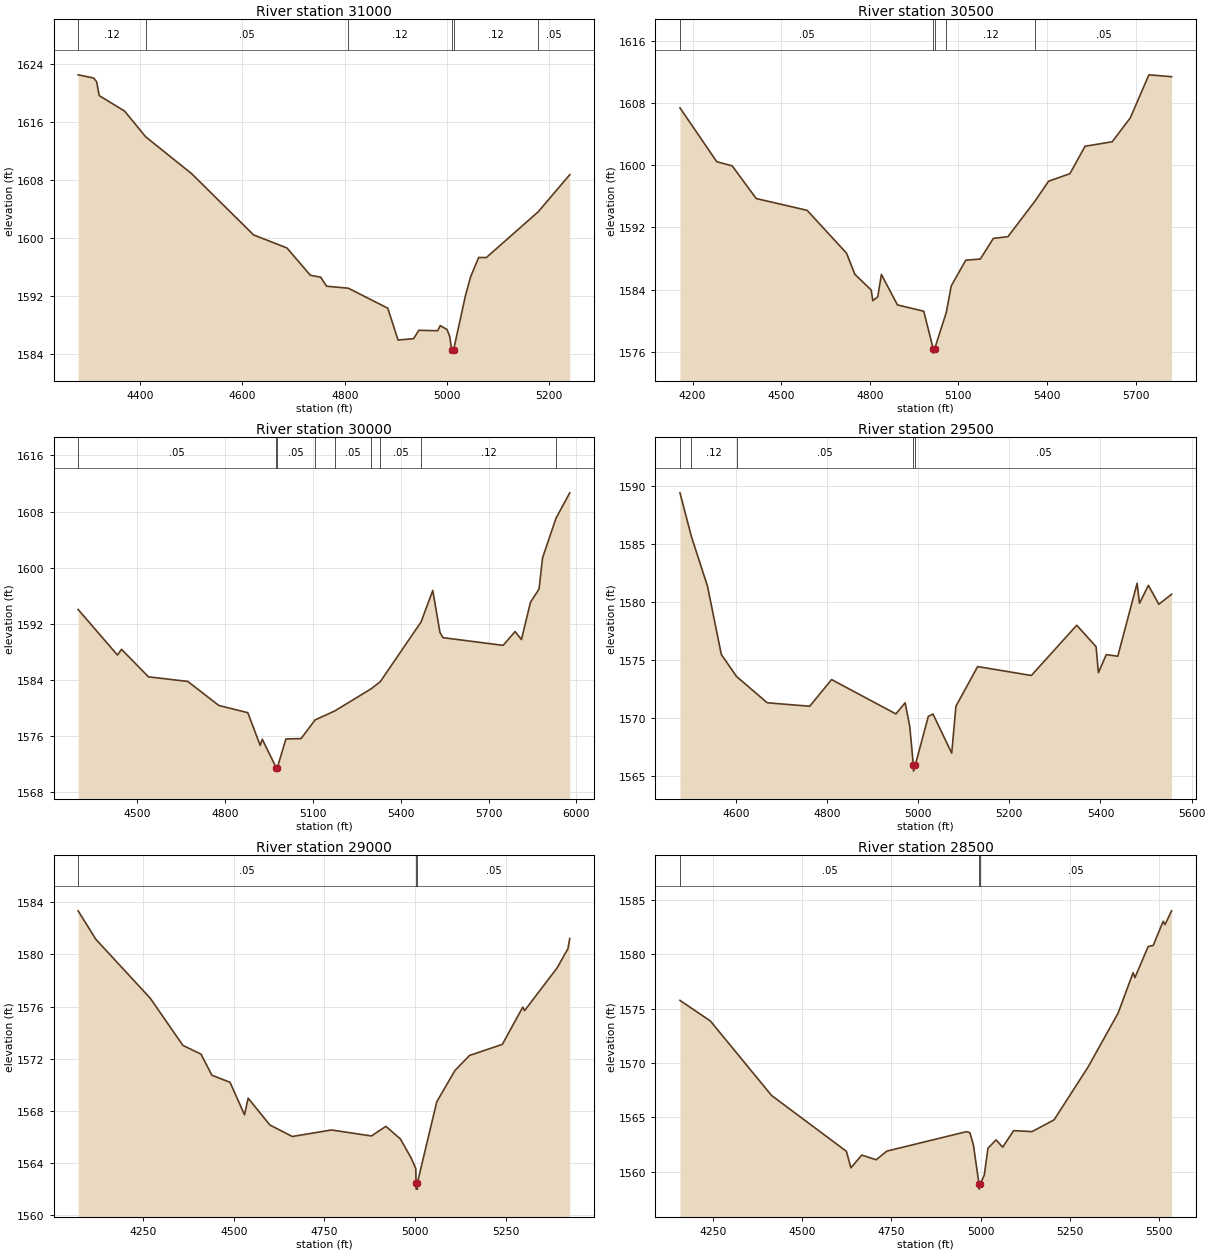
Type RM Length L Ch R = 1,31000,500,500,500
BEGIN DESCRIPTION:
LEFT HAND CREEK 62.0
END DESCRIPTION:
XS GIS Cut Line= 3
      2757055.70     10162653.11      2757770.52     10162750.36
      2758005.72     10162703.10
#Sta/Elev= 30
  4278.6 1622.57  4308.9 1622.13  4314.8 1621.62  4319.8 1619.71  4369.4 1617.57
  4410.8 1614.01  4500.6 1608.93  4621.7 1600.48  4687.0 1598.68  4732.7 1594.91
  4752.9 1594.65  4764.4 1593.40  4806.9 1593.13  4884.1 1590.37  4904.2 1585.98
  4934.6 1586.16  4944.7 1587.32  4981.7 1587.26  4986.7 1587.97  5000.0 1587.42
  5005.3 1586.46  5008.9 1584.67  5009.1 1584.17  5012.9 1584.67  5035.9 1592.08
  5046.1 1594.71  5061.8 1597.37  5076.7 1597.35  5178.5 1603.69  5239.9 1608.79
#Mann=6,-1,0
  4278.6    0.12       0  4410.8    0.05       0  4806.9    0.12       0
  5008.9    0.07       0  5012.9    0.12       0  5178.5    0.05       0
Bank Sta=5008.9,5012.9
Exp/Cntr=0.3,0.1

Type RM Length L Ch R = 1,30500,500,500,500
BEGIN DESCRIPTION:
LEFT HAND CREEK 61.0
END DESCRIPTION:
XS GIS Cut Line= 3
      2757067.95     10162842.47      2757818.93     10163224.58
      2758622.11     10163051.13
#Sta/Elev= 30
  4157.4 1607.40  4282.0 1600.46  4334.4 1599.92  4415.5 1595.72  4587.8 1594.20
  4721.3 1588.68  4749.5 1585.96  4804.7 1583.94  4810.3 1582.57  4826.9 1583.06
  4839.3 1585.94  4893.6 1582.02  4982.6 1581.21  5015.1 1576.31  5015.4 1575.81
  5019.1 1576.31  5059.0 1581.05  5075.7 1584.46  5125.0 1587.78  5174.2 1587.93
  5218.4 1590.59  5267.7 1590.81  5360.2 1595.44  5405.2 1597.95  5477.5 1598.92
  5528.7 1602.45  5620.7 1603.03  5682.1 1606.12  5744.9 1611.65  5821.7 1611.41
#Mann=5,-1,0
  4157.4    0.05       0  5015.1    0.05       0  5019.1    0.05       0
  5059.0    0.12       0  5360.2    0.05       0
Bank Sta=5015.1,5019.1
Exp/Cntr=0.3,0.1

Type RM Length L Ch R = 1,30000,500,500,500
BEGIN DESCRIPTION:
LEFT HAND CREEK 60.0
END DESCRIPTION:
XS GIS Cut Line= 3
      2757055.68     10163053.11      2757558.29     10163544.05
      2758505.73     10163303.10
#Sta/Elev= 30
  4297.4 1594.02  4431.8 1587.52  4445.9 1588.33  4537.8 1584.41  4672.3 1583.75
  4778.3 1580.32  4877.3 1579.29  4919.7 1574.62  4926.7 1575.50  4974.3 1571.45
  4974.5 1570.95  4978.3 1571.45  5007.6 1575.54  5059.2 1575.59  5107.3 1578.26
  5174.6 1579.54  5299.1 1582.71  5330.0 1583.71  5469.6 1592.25  5509.5 1596.74
  5533.9 1590.77  5544.2 1590.00  5749.9 1588.90  5790.8 1590.87  5812.5 1589.73
  5843.4 1595.05  5872.7 1596.94  5884.7 1601.40  5930.7 1607.05  5977.6 1610.67
#Mann=9,-1,0
  4297.4    0.05       0  4974.3    0.05       0  4978.3    0.05       0
  5107.3    0.12       0  5174.6    0.05       0  5299.1    0.12       0
  5330.0    0.05       0  5469.6    0.12       0  5930.7    0.05       0
Bank Sta=4974.3,4978.3
Exp/Cntr=0.3,0.1

Type RM Length L Ch R = 1,29500,500,500,500
BEGIN DESCRIPTION:
LEFT HAND CREEK 59.0
END DESCRIPTION:
XS GIS Cut Line= 3
      2757105.72     10163953.12      2757623.88     10164017.98
      2758165.20     10163891.10
#Sta/Elev= 30
  4477.8 1589.38  4503.0 1585.60  4538.2 1581.33  4568.5 1575.45  4602.0 1573.55
  4669.2 1571.29  4762.3 1570.99  4810.3 1573.29  4951.4 1570.33  4971.6 1571.29
  4981.7 1569.27  4989.7 1565.90  4990.0 1565.40  4993.7 1565.90  5022.4 1570.11
  5032.7 1570.32  5073.8 1566.95  5083.0 1570.99  5130.6 1574.41  5248.4 1573.64
  5348.0 1577.97  5390.4 1576.12  5395.5 1573.88  5412.7 1575.44  5438.0 1575.30
  5480.4 1581.59  5485.6 1579.86  5505.1 1581.41  5528.0 1579.78  5556.0 1580.64
#Mann=5,-1,0
  4477.8    0.05       0  4503.0    0.12       0  4602.0    0.05       0
  4989.7    0.05       0  4993.7    0.05       0
Bank Sta=4989.7,4993.7
Exp/Cntr=0.3,0.1

Type RM Length L Ch R = 1,29000,500,500,500
BEGIN DESCRIPTION:
LEFT HAND CREEK 58.0
END DESCRIPTION:
XS GIS Cut Line= 3
      2756866.63     10164474.43      2757795.67     10164448.63
      2758220.74     10164404.99
#Sta/Elev= 30
  4070.6 1583.35  4119.7 1581.16  4269.7 1576.64  4359.8 1573.02  4409.8 1572.35
  4439.8 1570.73  4489.8 1570.19  4529.8 1567.70  4539.8 1568.97  4599.9 1566.91
  4661.6 1566.03  4769.9 1566.53  4880.0 1566.07  4920.0 1566.81  4960.0 1565.84
  4990.0 1564.36  5002.5 1563.56  5003.0 1562.49  5003.3 1561.99  5006.8 1561.99
  5007.0 1562.49  5060.3 1568.69  5110.6 1571.10  5150.8 1572.25  5241.3 1573.10
  5297.7 1575.96  5302.7 1575.69  5391.9 1578.95  5422.2 1580.44  5427.3 1581.22
#Mann=3,-1,0
  4070.6    0.05       0  5003.0    0.05       0  5007.0    0.05       0
Bank Sta=5003,5007
Exp/Cntr=0.3,0.1

Type RM Length L Ch R = 1,28500,500,500,500
BEGIN DESCRIPTION:
LEFT HAND CREEK 57.0
END DESCRIPTION:
XS GIS Cut Line= 3
      2756901.30     10164766.10      2757735.59     10164877.51
      2758255.72     10164753.10
#Sta/Elev= 30
  4158.3 1575.76  4243.4 1573.87  4414.9 1567.01  4624.3 1561.88  4636.9 1560.36
  4667.2 1561.53  4707.5 1561.10  4737.8 1561.90  4959.7 1563.68  4969.8 1563.61
  4979.9 1562.46  4995.5 1558.90  4995.8 1558.40  4999.5 1558.90  5010.4 1559.70
  5020.7 1562.17  5043.4 1562.93  5061.8 1562.26  5092.6 1563.78  5144.0 1563.69
  5205.7 1564.77  5300.9 1569.63  5385.0 1574.59  5427.0 1578.31  5432.2 1577.86
  5469.1 1580.71  5483.4 1580.82  5511.2 1583.04  5516.3 1582.73  5534.8 1584.00
#Mann=3,-1,0
  4158.3    0.05       0  4995.5    0.05       0  4999.5    0.05       0
Bank Sta=4995.5,4999.5
Exp/Cntr=0.3,0.1

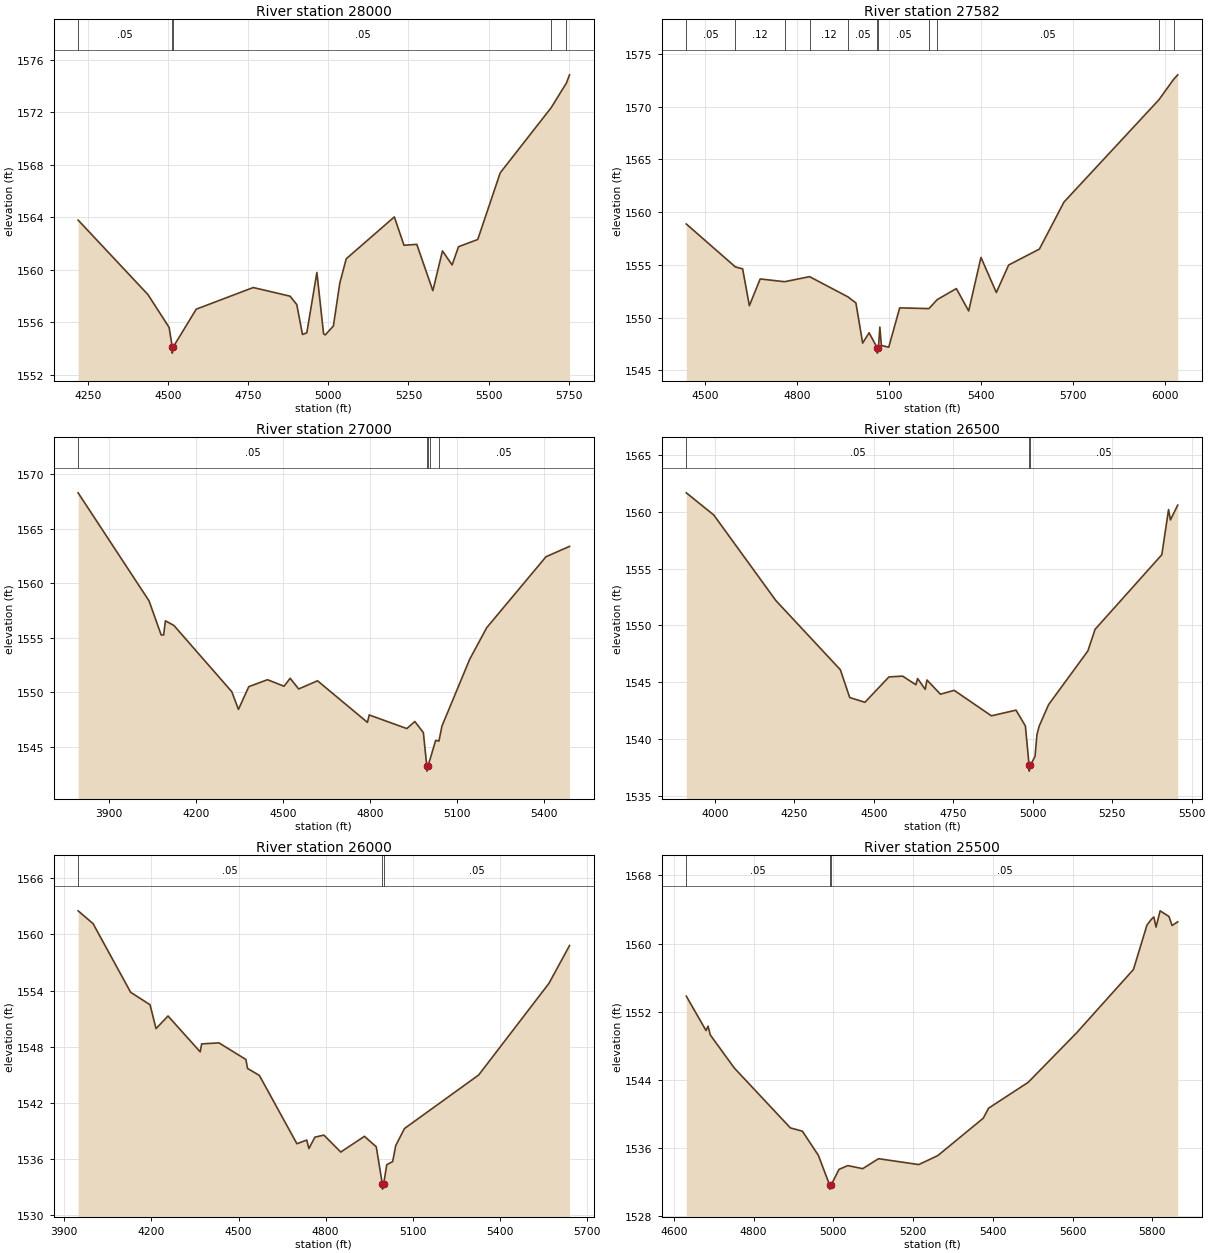
Type RM Length L Ch R = 1,28000,418,418,418
BEGIN DESCRIPTION:
LEFT HAND CREEK 56.0
END DESCRIPTION:
XS GIS Cut Line= 3
      2756942.96     10165064.70      2757689.59     10165290.76
      2758441.81     10165314.67
#Sta/Elev= 30
  4219.9 1563.78  4437.8 1558.10  4503.7 1555.60  4513.3 1554.14  4513.6 1553.64
  4517.3 1554.14  4588.4 1556.99  4766.1 1558.64  4881.0 1557.98  4901.9 1557.34
  4919.7 1555.06  4933.2 1555.19  4964.6 1559.79  4985.5 1555.11  4990.8 1555.03
  5016.1 1555.71  5036.1 1558.98  5056.1 1560.83  5206.2 1564.02  5236.3 1561.86
  5276.2 1561.93  5326.3 1558.40  5356.3 1561.43  5386.3 1560.36  5406.3 1561.75
  5466.3 1562.30  5536.4 1567.38  5695.4 1572.35  5742.7 1574.22  5752.6 1574.85
#Mann=5,-1,0
  4219.9    0.05       0  4513.3    0.05       0  4517.3    0.05       0
  5695.4    0.12       0  5742.7    0.05       0
Bank Sta=4513.3,4517.3
Exp/Cntr=0.3,0.1

Type RM Length L Ch R = 1,27582,582,582,582
BEGIN DESCRIPTION:
LEFT HAND CREEK 55.0
END DESCRIPTION:
XS GIS Cut Line= 3
      2757016.13     10165232.87      2757443.91     10165594.57
      2758483.18     10165657.83
#Sta/Elev= 30
  4439.8 1558.87  4599.8 1554.80  4623.3 1554.62  4645.3 1551.13  4680.5 1553.66
  4760.2 1553.40  4841.4 1553.88  4966.1 1551.97  4992.5 1551.39  5014.5 1547.58
  5035.4 1548.56  5061.9 1547.13  5062.2 1546.63  5065.9 1547.13  5070.5 1549.10
  5075.5 1547.36  5099.4 1547.19  5135.2 1550.92  5230.5 1550.85  5257.3 1551.70
  5319.8 1552.75  5359.9 1550.63  5400.0 1555.70  5450.1 1552.38  5490.1 1554.98
  5590.3 1556.49  5670.5 1560.95  5979.7 1570.64  6028.0 1572.59  6041.2 1573.01
#Mann=11,-1,0
  4439.8    0.05       0  4599.8    0.12       0  4760.2    0.05       0
  4841.4    0.12       0  4966.1    0.05       0  5061.9    0.05       0
  5065.9    0.05       0  5230.5    0.12       0  5257.3    0.05       0
  5979.7    0.12       0  6028.0    0.05       0
Bank Sta=5061.9,5065.9
Exp/Cntr=0.3,0.1

Type RM Length L Ch R = 1,27000,500,500,500
BEGIN DESCRIPTION:
LEFT HAND CREEK 54.0
END DESCRIPTION:
XS GIS Cut Line= 3
      2756655.67     10165053.09      2757359.38     10166032.73
      2757605.67     10166453.09
#Sta/Elev= 30
  3793.8 1568.31  4038.1 1558.39  4079.9 1555.26  4088.5 1555.24  4094.6 1556.55
  4124.1 1556.12  4323.3 1550.04  4346.3 1548.41  4381.9 1550.50  4446.4 1551.14
  4503.5 1550.54  4524.4 1551.27  4553.8 1550.29  4618.8 1551.04  4790.8 1547.22
  4796.9 1547.90  4926.6 1546.65  4954.1 1547.30  4983.5 1546.28  4995.2 1543.24
  4995.4 1542.74  4999.2 1543.24  5006.9 1543.86  5025.9 1545.57  5037.2 1545.50
  5047.4 1546.87  5143.2 1553.02  5201.8 1555.92  5406.1 1562.44  5487.2 1563.39
#Mann=5,-1,0
  3793.8    0.05       0  4995.2    0.05       0  4999.2    0.05       0
  5006.9    0.12       0  5037.2    0.05       0
Bank Sta=4995.2,4999.2
Exp/Cntr=0.3,0.1

Type RM Length L Ch R = 1,26500,500,500,500
BEGIN DESCRIPTION:
LEFT HAND CREEK 53.0
END DESCRIPTION:
XS GIS Cut Line= 3
      2756555.67     10165253.09      2756968.42     10166261.70
      2757355.65     10166503.09
#Sta/Elev= 30
  3910.2 1561.66  3996.7 1559.71  4192.0 1552.19  4394.9 1546.11  4424.3 1543.67
  4472.1 1543.25  4547.7 1545.48  4590.9 1545.55  4632.5 1544.79  4637.9 1545.34
  4661.9 1544.39  4667.3 1545.21  4709.8 1543.96  4753.0 1544.30  4870.2 1542.06
  4947.5 1542.56  4977.0 1541.17  4988.7 1537.70  4989.0 1537.20  4992.7 1537.70
  5007.4 1538.50  5013.3 1540.40  5020.3 1541.15  5049.9 1543.04  5173.5 1547.76
  5196.2 1549.66  5406.2 1556.22  5427.4 1560.19  5433.3 1559.28  5456.3 1560.58
#Mann=3,-1,0
  3910.2    0.05       0  4988.7    0.05       0  4992.7    0.05       0
Bank Sta=4988.7,4992.7
Exp/Cntr=0.3,0.1

Type RM Length L Ch R = 1,26000,500,500,500
BEGIN DESCRIPTION:
LEFT HAND CREEK 52.0
END DESCRIPTION:
XS GIS Cut Line= 3
      2756255.68     10165353.10      2756517.04     10166372.63
      2756405.69     10167003.07
#Sta/Elev= 30
  3947.5 1562.51  3999.1 1561.14  4128.5 1553.81  4195.3 1552.48  4215.9 1549.93
  4257.2 1551.28  4368.0 1547.45  4373.1 1548.30  4432.7 1548.41  4525.6 1546.63
  4531.1 1545.68  4571.9 1544.93  4701.1 1537.64  4735.0 1538.03  4742.4 1537.12
  4763.1 1538.34  4794.0 1538.56  4852.2 1536.75  4933.8 1538.43  4974.5 1537.31
  4995.7 1533.29  4995.9 1532.79  4999.7 1533.29  5010.6 1535.40  5031.0 1535.73
  5041.4 1537.43  5071.6 1539.26  5327.3 1544.98  5569.2 1554.76  5640.2 1558.80
#Mann=3,-1,0
  3947.5    0.05       0  4995.7    0.05       0  4999.7    0.05       0
Bank Sta=4995.7,4999.7
Exp/Cntr=0.3,0.1

Type RM Length L Ch R = 1,25500,500,500,500
BEGIN DESCRIPTION:
LEFT HAND CREEK 51.0
END DESCRIPTION:
XS GIS Cut Line= 3
      2756005.69     10165953.15      2756039.96     10166320.36
      2756405.69     10167103.13
#Sta/Elev= 30
  4631.2 1553.83  4680.7 1549.80  4685.7 1550.31  4691.4 1549.28  4751.7 1545.40
  4892.3 1538.38  4922.4 1538.00  4962.6 1535.15  4990.6 1531.70  4990.9 1531.20
  4994.8 1531.70  5014.1 1533.51  5036.2 1533.96  5073.7 1533.60  5113.4 1534.77
  5214.3 1534.08  5262.0 1535.13  5376.2 1539.52  5389.4 1540.69  5488.7 1543.72
  5610.1 1549.52  5752.9 1556.96  5786.8 1562.17  5797.8 1562.84  5804.1 1563.11
  5809.6 1561.93  5819.8 1563.84  5841.9 1563.18  5849.8 1562.12  5864.0 1562.55
#Mann=3,-1,0
  4631.2    0.05       0  4990.6    0.05       0  4994.8    0.05       0
Bank Sta=4990.6,4994.8
Exp/Cntr=0.3,0.1

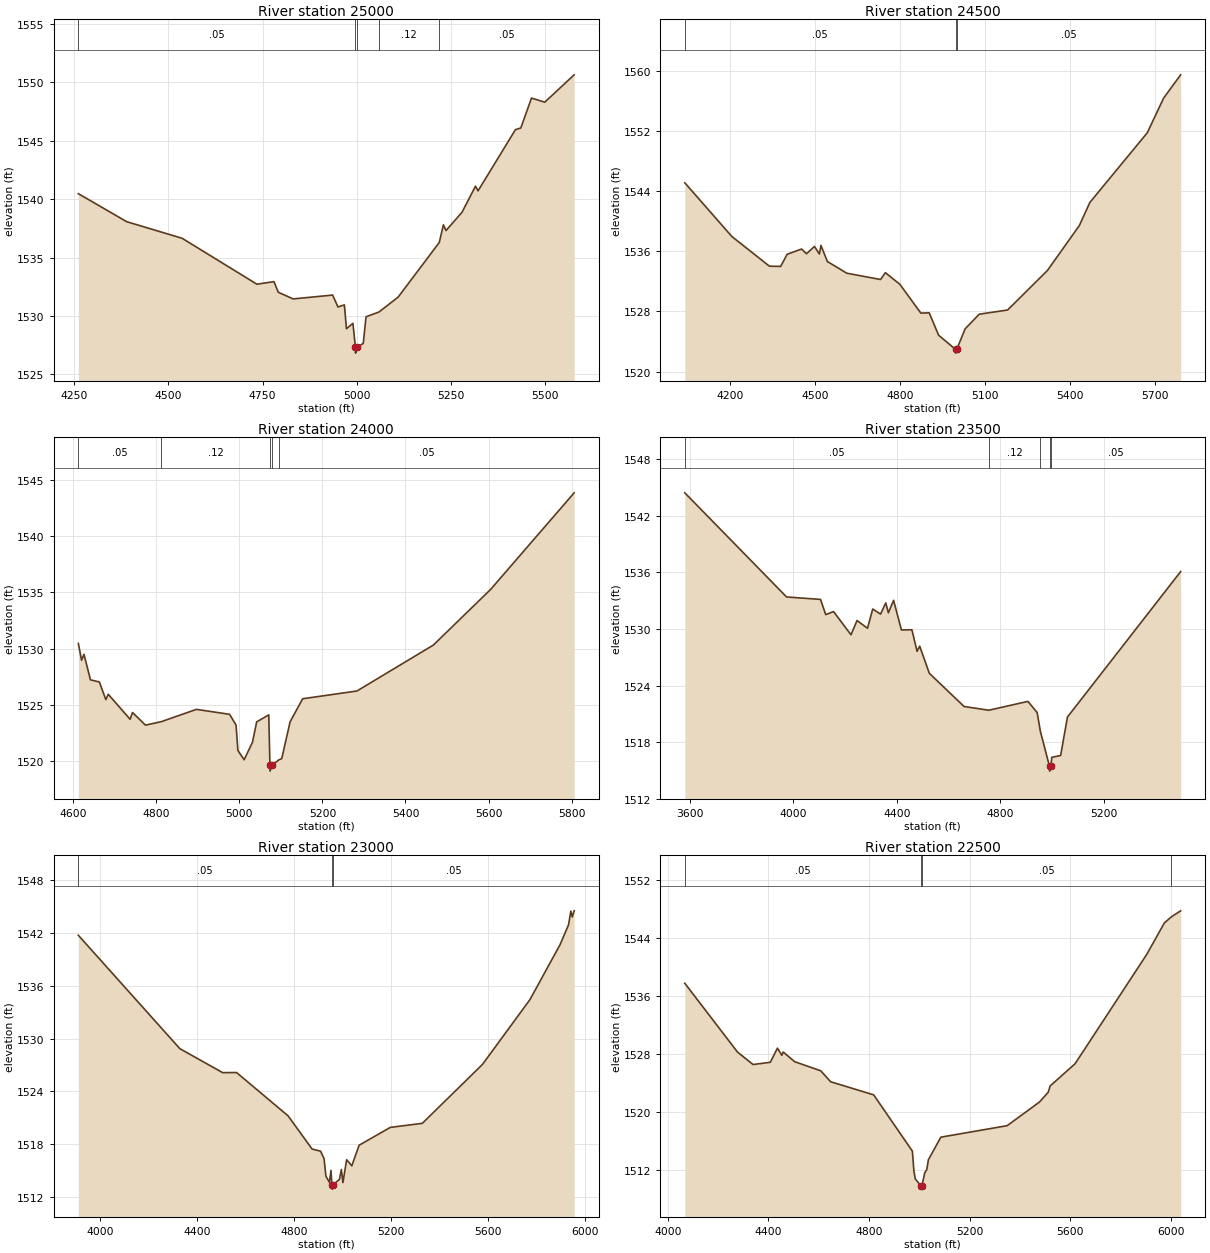
Type RM Length L Ch R = 1,25000,500,500,500
BEGIN DESCRIPTION:
LEFT HAND CREEK 50.0
END DESCRIPTION:
XS GIS Cut Line= 3
      2755463.82     10165995.29      2755783.49     10166660.80
      2756205.66     10167053.09
#Sta/Elev= 30
  4261.7 1540.47  4389.9 1538.07  4536.9 1536.65  4735.1 1532.72  4780.4 1532.94
  4791.8 1532.03  4831.2 1531.46  4936.0 1531.79  4950.0 1530.77  4967.1 1530.95
  4972.6 1528.91  4989.7 1529.37  4996.4 1527.32  4996.7 1526.82  5000.6 1527.32
  5017.1 1527.65  5024.5 1529.93  5058.8 1530.34  5109.5 1531.61  5218.7 1536.29
  5229.7 1537.80  5236.5 1537.31  5279.0 1538.88  5314.7 1541.11  5321.5 1540.71
  5420.7 1545.95  5434.9 1546.09  5463.2 1548.65  5498.4 1548.30  5576.3 1550.64
#Mann=5,-1,0
  4261.7    0.05       0  4996.4    0.05       0  5000.6    0.05       0
  5058.8    0.12       0  5218.7    0.05       0
Bank Sta=4996.4,5000.6
Exp/Cntr=0.3,0.1

Type RM Length L Ch R = 1,24500,500,500,500
BEGIN DESCRIPTION:
LEFT HAND CREEK 49.0
END DESCRIPTION:
XS GIS Cut Line= 3
      2755155.68     10166203.09      2755565.32     10167070.09
      2756355.73     10167103.11
#Sta/Elev= 30
  4041.1 1545.10  4207.0 1537.97  4339.7 1534.02  4379.5 1533.99  4402.3 1535.60
  4453.3 1536.30  4470.6 1535.67  4498.8 1536.64  4516.1 1535.64  4521.6 1536.78
  4544.4 1534.64  4612.7 1533.09  4732.0 1532.25  4749.0 1533.16  4800.3 1531.61
  4874.1 1527.79  4903.8 1527.82  4936.9 1524.85  4996.7 1522.97  4997.0 1522.47
  5001.1 1522.97  5030.4 1525.69  5080.4 1527.64  5180.5 1528.20  5320.6 1533.43
  5433.7 1539.42  5470.8 1542.49  5673.6 1551.75  5731.0 1556.34  5791.1 1559.44
#Mann=3,-1,0
  4041.1    0.05       0  4996.7    0.05       0  5001.1    0.05       0
Bank Sta=4996.7,5001.1
Exp/Cntr=0.3,0.1

Type RM Length L Ch R = 1,24000,500,500,500
BEGIN DESCRIPTION:
LEFT HAND CREEK 48.0
END DESCRIPTION:
XS GIS Cut Line= 3
      2755205.70     10167103.13      2755404.02     10167435.81
      2756205.66     10167353.11
#Sta/Elev= 30
  4612.7 1530.47  4620.5 1528.98  4626.3 1529.50  4641.9 1527.24  4663.3 1527.05
  4678.9 1525.48  4684.7 1525.96  4737.3 1523.74  4743.1 1524.34  4774.3 1523.22
  4812.5 1523.53  4896.9 1524.62  4976.7 1524.18  4992.3 1523.22  4996.7 1520.97
  5011.7 1520.15  5031.8 1521.70  5041.9 1523.51  5071.0 1524.13  5073.8 1519.64
  5074.1 1519.14  5078.2 1519.64  5095.3 1520.14  5102.2 1520.25  5122.3 1523.51
  5152.5 1525.56  5283.2 1526.25  5467.0 1530.32  5604.9 1535.26  5805.9 1543.83
#Mann=5,-1,0
  4612.7    0.05       0  4812.5    0.12       0  5073.8    0.07       0
  5078.2    0.12       0  5095.3    0.05       0
Bank Sta=5073.8,5078.2
Exp/Cntr=0.3,0.1

Type RM Length L Ch R = 1,23500,500,500,500
BEGIN DESCRIPTION:
LEFT HAND CREEK 47.0
END DESCRIPTION:
XS GIS Cut Line= 3
      2755055.69     10166203.14      2755243.01     10167609.92
      2755305.69     10168103.15
#Sta/Elev= 30
  3580.8 1544.45  3974.2 1533.40  4105.4 1533.14  4125.5 1531.53  4155.8 1531.85
  4223.1 1529.39  4246.6 1530.90  4287.0 1530.08  4307.1 1532.12  4337.4 1531.58
  4357.6 1532.77  4367.7 1531.72  4387.8 1533.04  4418.1 1529.90  4458.5 1529.92
  4478.6 1527.63  4488.7 1528.18  4525.9 1525.30  4660.2 1521.78  4755.6 1521.38
  4907.0 1522.32  4942.7 1521.14  4955.1 1519.15  4990.5 1515.42  4990.9 1514.92
  4995.8 1515.42  4999.1 1516.38  5033.5 1516.58  5059.8 1520.66  5497.2 1536.09
#Mann=5,-1,0
  3580.8    0.05       0  4755.6    0.12       0  4955.1    0.05       0
  4990.5    0.03       0  4995.8    0.05       0
Bank Sta=4990.5,4995.8
Exp/Cntr=0.3,0.1

Type RM Length L Ch R = 1,23000,500,500,500
BEGIN DESCRIPTION:
LEFT HAND CREEK 46.0
END DESCRIPTION:
XS GIS Cut Line= 3
      2754105.66     10166603.08      2754811.01     10167433.82
      2755305.66     10168253.07
#Sta/Elev= 30
  3910.2 1541.74  4329.3 1528.85  4506.1 1526.12  4563.2 1526.14  4776.1 1521.21
  4875.2 1517.44  4910.3 1517.19  4924.6 1516.34  4932.3 1514.36  4938.9 1514.02
  4946.6 1513.66  4953.1 1515.01  4957.0 1513.38  4957.4 1512.88  4962.4 1513.38
  4988.3 1514.00  4996.0 1515.11  5002.5 1513.62  5017.7 1516.22  5039.1 1515.53
  5069.3 1517.87  5198.2 1519.90  5330.2 1520.36  5578.6 1527.06  5774.6 1534.43
  5898.6 1540.66  5933.8 1542.93  5943.4 1544.49  5949.3 1543.82  5957.0 1544.52
#Mann=3,-1,0
  3910.2    0.05       0  4957.0    0.05       0  4962.4    0.05       0
Bank Sta=4957,4962.4
Exp/Cntr=0.3,0.1

Type RM Length L Ch R = 1,22500,500,500,500
BEGIN DESCRIPTION:
LEFT HAND CREEK 45.0
END DESCRIPTION:
XS GIS Cut Line= 3
      2754105.67     10166853.09      2754499.33     10167697.98
      2755305.65     10168353.09
#Sta/Elev= 30
  4067.9 1537.74  4277.5 1528.23  4339.2 1526.51  4407.8 1526.82  4436.2 1528.77
  4453.6 1527.78  4459.1 1528.24  4504.8 1526.90  4608.5 1525.64  4647.6 1524.13
  4818.7 1522.32  4972.6 1514.54  4978.8 1511.75  4984.3 1510.69  5005.5 1509.79
  5005.9 1509.29  5010.9 1509.79  5021.8 1511.55  5029.7 1511.96  5036.2 1513.34
  5085.7 1516.47  5349.4 1518.06  5477.2 1521.31  5512.4 1522.67  5520.3 1523.55
  5619.4 1526.62  5903.9 1541.71  5974.5 1546.09  6002.2 1546.92  6038.9 1547.75
#Mann=4,-1,0
  4067.9    0.05       0  5005.5    0.05       0  5010.9    0.05       0
  6002.2    0.12       0
Bank Sta=5005.5,5010.9
Exp/Cntr=0.3,0.1

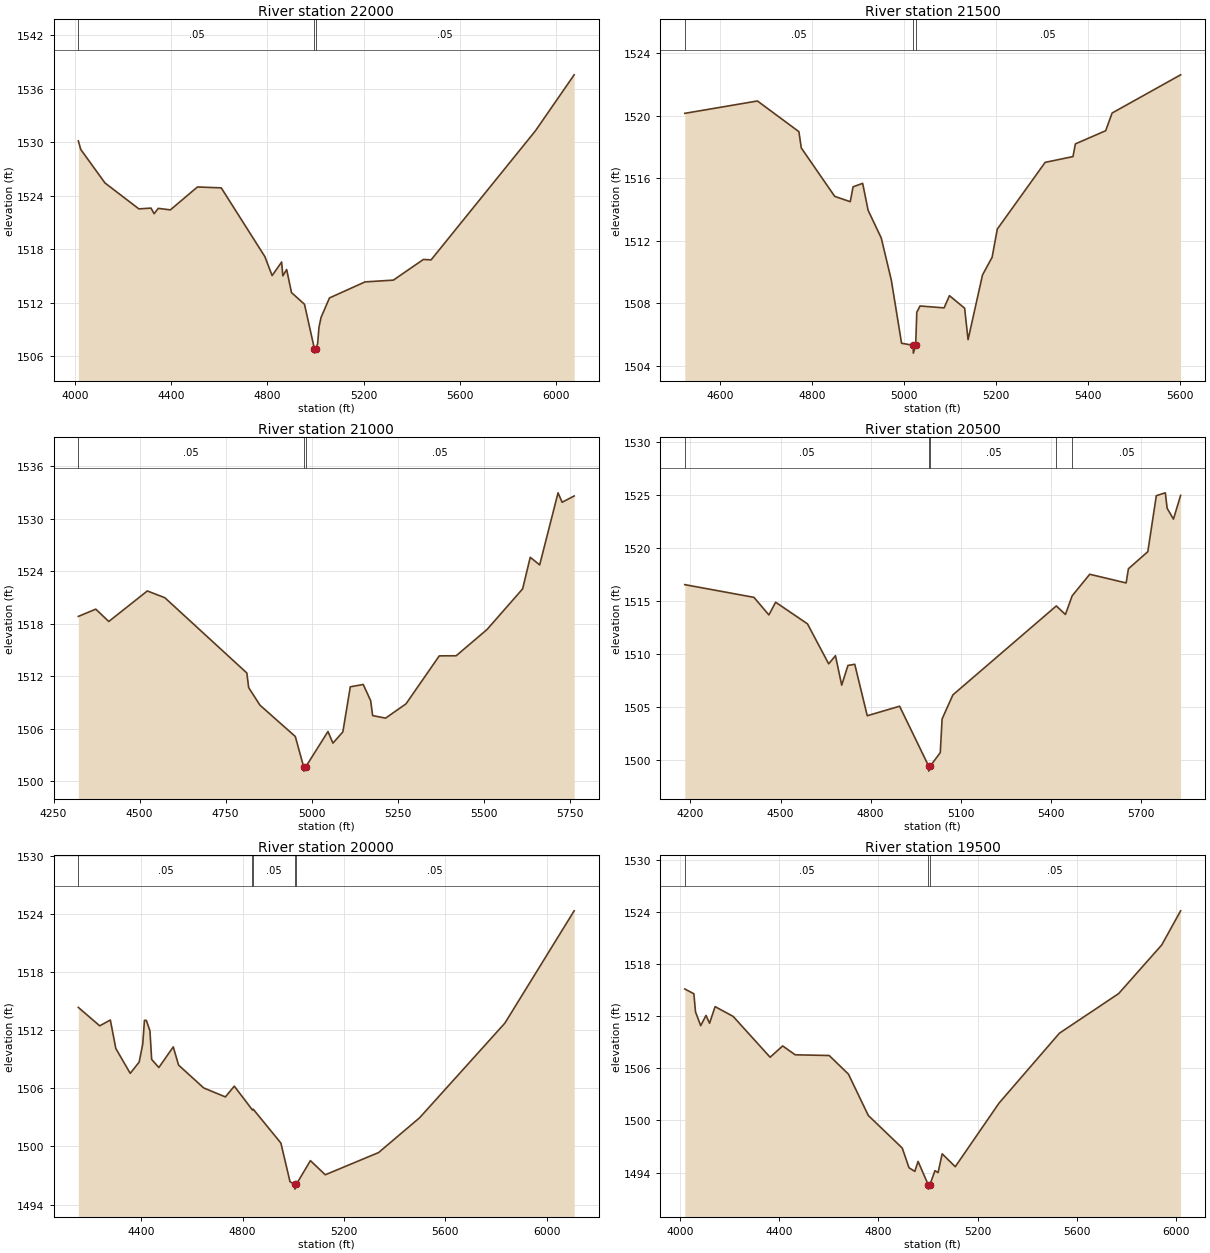
Type RM Length L Ch R = 1,22000,500,500,500
BEGIN DESCRIPTION:
LEFT HAND CREEK 44.0
END DESCRIPTION:
XS GIS Cut Line= 3
      2754005.68     10167003.09      2754116.00     10167982.60
      2755055.67     10168503.10
#Sta/Elev= 30
  4014.3 1530.16  4024.4 1529.20  4125.0 1525.44  4265.9 1522.53  4316.2 1522.62
  4329.2 1521.99  4346.4 1522.59  4396.7 1522.42  4509.1 1524.99  4608.1 1524.89
  4789.2 1517.18  4819.4 1515.05  4858.9 1516.57  4863.9 1515.02  4879.8 1515.73
  4899.9 1513.14  4953.9 1511.83  4995.0 1506.85  4995.4 1506.35  5000.5 1506.85
  5008.4 1507.40  5014.1 1509.25  5022.5 1510.34  5057.6 1512.54  5205.4 1514.34
  5323.2 1514.54  5448.0 1516.86  5479.8 1516.81  5913.9 1531.31  6074.2 1537.57
#Mann=3,-1,0
  4014.3    0.05       0  4995.0    0.05       0  5000.5    0.05       0
Bank Sta=4995,5000.5
Exp/Cntr=0.3,0.1

Type RM Length L Ch R = 1,21500,500,500,500
BEGIN DESCRIPTION:
LEFT HAND CREEK 43.0
END DESCRIPTION:
XS GIS Cut Line= 3
      2753831.86     10167891.09      2753963.14     10168349.56
      2754137.41     10168925.79
#Sta/Elev= 30
  4523.1 1520.14  4681.2 1520.93  4771.4 1518.97  4776.6 1517.93  4849.3 1514.84
  4883.1 1514.50  4889.3 1515.45  4910.1 1515.67  4922.0 1513.95  4950.6 1512.18
  4972.5 1509.49  4994.8 1505.46  5020.0 1505.33  5020.4 1504.83  5025.5 1505.33
  5027.9 1507.44  5035.0 1507.84  5087.3 1507.72  5099.0 1508.50  5132.0 1507.70
  5139.5 1505.69  5170.9 1509.82  5191.8 1510.95  5203.1 1512.75  5307.2 1517.01
  5367.8 1517.38  5373.0 1518.19  5438.9 1519.03  5452.9 1520.16  5602.0 1522.60
#Mann=3,-1,0
  4523.1    0.05       0  5020.0    0.05       0  5025.5    0.05       0
Bank Sta=5020,5025.5
Exp/Cntr=0.3,0.1

Type RM Length L Ch R = 1,21000,500,500,500
BEGIN DESCRIPTION:
LEFT HAND CREEK 42.0
END DESCRIPTION:
XS GIS Cut Line= 3
      2753776.30     10167821.67      2753575.26     10168469.18
      2753200.31     10169133.47
#Sta/Elev= 30
  4322.0 1518.82  4372.7 1519.65  4410.5 1518.24  4522.5 1521.73  4573.3 1520.96
  4811.7 1512.35  4817.0 1510.68  4849.6 1508.68  4952.5 1505.09  4976.7 1501.63
  4977.2 1501.13  4983.0 1501.63  5047.4 1505.66  5061.9 1504.33  5090.7 1505.62
  5112.3 1510.77  5149.9 1511.04  5171.5 1509.18  5177.3 1507.48  5214.9 1507.19
  5274.1 1508.82  5370.9 1514.31  5419.9 1514.32  5509.8 1517.33  5613.1 1521.97
  5635.2 1525.58  5662.6 1524.71  5716.0 1532.95  5727.9 1531.87  5762.8 1532.59
#Mann=3,-1,0
  4322.0    0.05       0  4976.7    0.05       0  4983.0    0.05       0
Bank Sta=4976.7,4983
Exp/Cntr=0.3,0.1

Type RM Length L Ch R = 1,20500,500,500,500
BEGIN DESCRIPTION:
LEFT HAND CREEK 41.0
END DESCRIPTION:
XS GIS Cut Line= 3
      2753699.95     10167703.56      2753199.25     10168351.69
      2752734.62     10169043.91
#Sta/Elev= 30
  4181.0 1516.56  4411.5 1515.36  4461.3 1513.70  4483.7 1514.90  4589.9 1512.86
  4660.6 1509.08  4683.2 1509.85  4704.0 1507.07  4724.8 1508.93  4747.5 1509.04
  4789.2 1504.18  4897.0 1505.08  4993.4 1499.45  4993.9 1498.95  4999.8 1499.45
  5032.6 1500.70  5038.6 1503.87  5074.6 1506.15  5419.4 1514.55  5449.7 1513.74
  5472.1 1515.50  5530.7 1517.54  5652.1 1516.72  5659.7 1518.06  5724.3 1519.67
  5752.7 1524.96  5782.7 1525.23  5788.8 1523.77  5809.8 1522.75  5833.7 1524.99
#Mann=5,-1,0
  4181.0    0.05       0  4993.4    0.05       0  4999.8    0.05       0
  5419.4    0.12       0  5472.1    0.05       0
Bank Sta=4993.4,4999.8
Exp/Cntr=0.3,0.1

Type RM Length L Ch R = 1,20000,500,500,500
BEGIN DESCRIPTION:
LEFT HAND CREEK 40.0
END DESCRIPTION:
XS GIS Cut Line= 3
      2753470.75     10167349.43      2752906.48     10167982.85
      2752346.24     10168938.89
#Sta/Elev= 30
  4151.7 1514.34  4236.1 1512.44  4278.0 1513.04  4299.7 1510.10  4356.5 1507.54
  4391.7 1508.70  4405.9 1510.56  4412.6 1513.01  4420.1 1513.00  4434.3 1511.93
  4441.0 1508.98  4469.4 1508.14  4526.3 1510.27  4547.2 1508.39  4646.7 1506.03
  4732.0 1505.11  4767.1 1506.22  4838.7 1503.76  4841.9 1503.84  4951.0 1500.35
  4987.0 1496.36  5005.5 1496.10  5006.0 1495.60  5012.0 1496.10  5067.4 1498.54
  5126.1 1497.08  5336.4 1499.37  5498.7 1502.97  5834.8 1512.72  6108.1 1524.30
#Mann=5,-1,0
  4151.7    0.05       0  4838.7    0.12       0  4841.9    0.05       0
  5005.5    0.05       0  5012.0    0.05       0
Bank Sta=5005.5,5012
Exp/Cntr=0.3,0.1

Type RM Length L Ch R = 1,19500,500,500,500
BEGIN DESCRIPTION:
LEFT HAND CREEK 39.0
END DESCRIPTION:
XS GIS Cut Line= 3
      2753255.69     10167253.11      2752453.13     10167815.34
      2752055.69     10168753.09
#Sta/Elev= 30
  4020.1 1515.11  4056.7 1514.56  4063.3 1512.48  4084.2 1510.89  4105.6 1512.07
  4119.9 1511.17  4142.2 1513.08  4214.9 1511.96  4364.0 1507.26  4414.6 1508.56
  4465.1 1507.54  4602.0 1507.46  4679.6 1505.32  4759.8 1500.56  4896.7 1496.81
  4923.7 1494.55  4947.2 1494.13  4960.3 1495.28  5001.3 1492.59  5001.8 1492.09
  5007.9 1492.59  5028.3 1494.21  5041.0 1493.99  5057.4 1496.15  5110.2 1494.67
  5286.8 1501.99  5529.8 1510.02  5768.7 1514.58  5942.5 1520.18  6018.5 1524.10
#Mann=3,-1,0
  4020.1    0.05       0  5001.3    0.05       0  5007.9    0.05       0
Bank Sta=5001.3,5007.9
Exp/Cntr=0.3,0.1