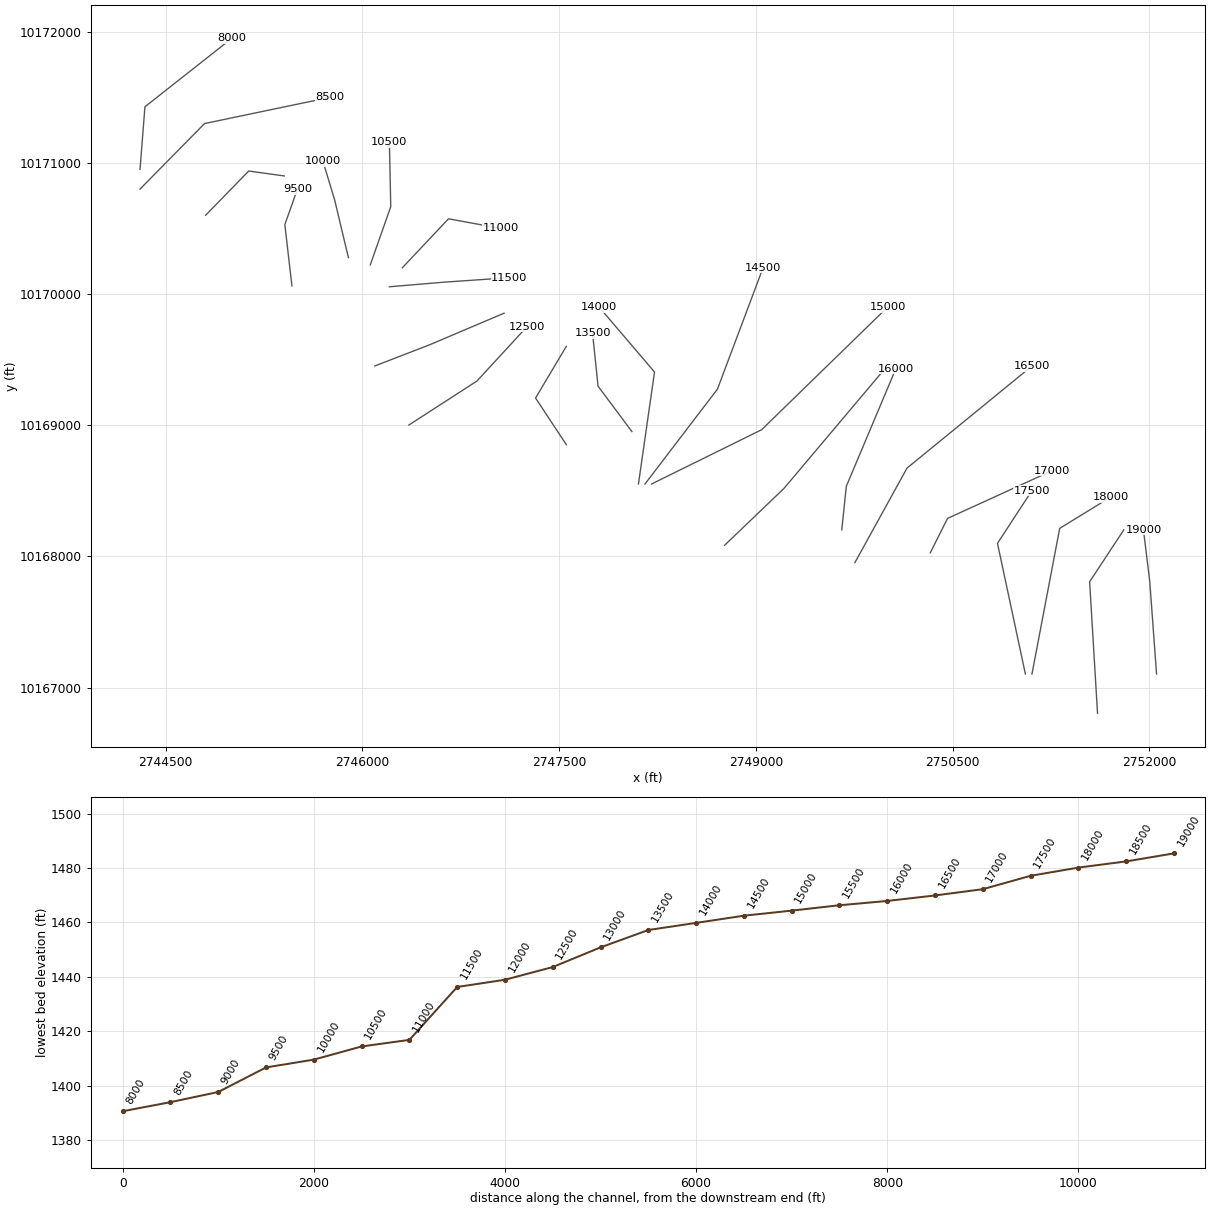
HEC-RAS study LEFT HAND CREEK.prj: LEFT HAND CREEK Base Level Engineering

--- LEFT HAND CREEK.g01 (geometry) --- (continued)

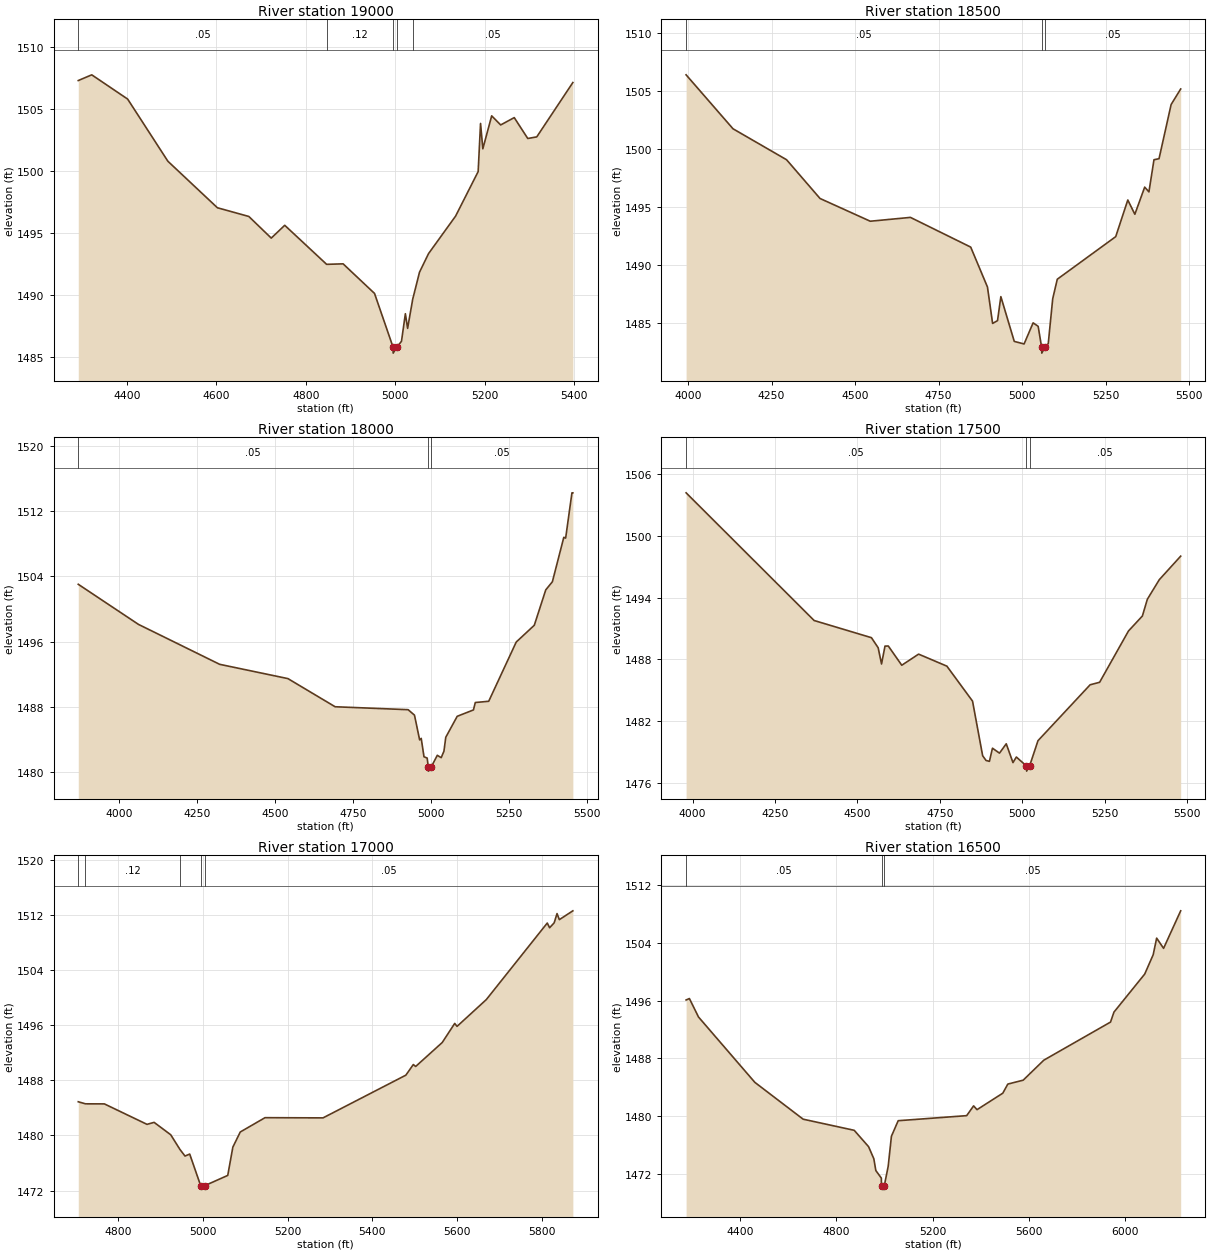
Type RM Length L Ch R = 1,19000,500,500,500
BEGIN DESCRIPTION:
LEFT HAND CREEK 38.0
END DESCRIPTION:
XS GIS Cut Line= 3
      2752055.68     10167103.12      2752003.85     10167809.42
      2751955.69     10168203.08
#Sta/Elev= 30
  4291.8 1507.27  4321.9 1507.73  4402.1 1505.78  4492.0 1500.78  4602.6 1497.04
  4672.8 1496.34  4722.9 1494.60  4753.0 1495.63  4846.6 1492.49  4883.4 1492.53
  4953.6 1490.15  4994.8 1485.85  4995.3 1485.35  5003.8 1485.85  5013.8 1486.30
  5022.5 1488.52  5027.5 1487.34  5038.9 1489.69  5054.1 1491.86  5074.2 1493.35
  5134.7 1496.37  5185.1 1499.95  5190.4 1503.82  5195.5 1501.78  5215.3 1504.43
  5235.4 1503.70  5265.7 1504.29  5295.9 1502.61  5316.0 1502.74  5396.6 1507.11
#Mann=5,-1,0
  4291.8    0.05       0  4846.6    0.12       0  4994.8    0.07       0
  5003.8    0.12       0  5038.9    0.05       0
Bank Sta=4994.8,5003.8
Exp/Cntr=0.3,0.1

Type RM Length L Ch R = 1,18500,500,500,500
BEGIN DESCRIPTION:
LEFT HAND CREEK 37.0
END DESCRIPTION:
XS GIS Cut Line= 3
      2751605.69     10166803.10      2751545.39     10167806.89
      2751805.70     10168203.13
#Sta/Elev= 30
  3994.4 1506.40  4134.7 1501.75  4295.0 1499.08  4395.1 1495.74  4545.4 1493.78
  4665.6 1494.11  4845.9 1491.55  4896.0 1488.11  4911.4 1484.97  4926.1 1485.21
  4936.1 1487.28  4976.2 1483.42  5005.6 1483.20  5032.6 1485.02  5047.7 1484.72
  5058.1 1482.91  5058.6 1482.41  5067.4 1482.91  5077.9 1483.23  5091.2 1487.09
  5104.9 1488.78  5279.7 1492.45  5315.9 1495.61  5337.0 1494.38  5366.4 1496.72
  5379.1 1496.31  5394.2 1499.08  5409.3 1499.17  5445.5 1503.84  5474.1 1505.18
#Mann=3,-1,0
  3994.4    0.05       0  5058.1    0.05       0  5067.4    0.05       0
Bank Sta=5058.1,5067.4
Exp/Cntr=0.3,0.1

Type RM Length L Ch R = 1,18000,500,500,500
BEGIN DESCRIPTION:
LEFT HAND CREEK 36.0
END DESCRIPTION:
XS GIS Cut Line= 3
      2751105.69     10167103.16      2751317.10     10168214.33
      2751705.69     10168453.12
#Sta/Elev= 30
  3868.9 1503.04  4062.3 1498.12  4322.7 1493.23  4541.7 1491.48  4693.2 1488.03
  4927.5 1487.67  4947.9 1487.00  4964.4 1483.97  4969.5 1484.15  4978.4 1481.90
  4988.6 1481.74  4992.1 1480.64  4992.6 1480.14  5001.5 1480.64  5021.1 1482.08
  5033.6 1481.79  5042.4 1482.58  5048.3 1484.29  5085.0 1486.86  5137.1 1487.64
  5143.0 1488.55  5186.1 1488.70  5274.4 1495.96  5332.4 1498.02  5369.1 1502.35
  5390.4 1503.35  5427.1 1508.80  5433.0 1508.70  5453.2 1514.25  5456.1 1514.25
#Mann=3,-1,0
  3868.9    0.05       0  4992.1    0.05       0  5001.5    0.05       0
Bank Sta=4992.1,5001.5
Exp/Cntr=0.3,0.1

Type RM Length L Ch R = 1,17500,500,500,500
BEGIN DESCRIPTION:
LEFT HAND CREEK 35.0
END DESCRIPTION:
XS GIS Cut Line= 3
      2751055.68     10167103.14      2750842.78     10168100.26
      2751105.71     10168503.15
#Sta/Elev= 30
  3980.4 1504.19  4368.9 1491.77  4542.8 1490.10  4563.2 1489.12  4573.4 1487.54
  4583.9 1489.28  4593.9 1489.29  4634.8 1487.42  4685.9 1488.50  4771.7 1487.33
  4849.5 1483.93  4880.2 1478.62  4890.4 1478.16  4900.7 1478.07  4910.0 1479.35
  4931.3 1478.87  4951.8 1479.78  4972.2 1477.95  4982.5 1478.49  5013.2 1477.62
  5013.7 1477.12  5022.6 1477.62  5048.1 1480.08  5206.4 1485.52  5235.1 1485.76
  5322.7 1490.75  5364.9 1492.21  5380.0 1493.84  5416.2 1495.74  5481.1 1498.03
#Mann=3,-1,0
  3980.4    0.05       0  5013.2    0.05       0  5022.6    0.05       0
Bank Sta=5013.2,5022.6
Exp/Cntr=0.3,0.1

Type RM Length L Ch R = 1,17000,500,500,500
BEGIN DESCRIPTION:
LEFT HAND CREEK 34.0
END DESCRIPTION:
XS GIS Cut Line= 3
      2750330.69     10168028.12      2750461.94     10168290.41
      2751255.70     10168653.12
#Sta/Elev= 30
  4706.7 1484.89  4723.6 1484.59  4768.2 1484.58  4868.8 1481.61  4885.5 1481.90
  4924.7 1480.10  4946.3 1477.98  4958.3 1477.01  4969.4 1477.30  4995.3 1472.71
  4995.8 1472.21  5004.8 1472.71  5059.1 1474.20  5071.1 1478.30  5088.6 1480.50
  5147.0 1482.58  5283.8 1482.55  5479.0 1488.75  5496.6 1490.29  5502.1 1490.01
  5564.8 1493.49  5594.2 1496.26  5599.7 1495.83  5668.7 1499.72  5812.4 1510.83
  5817.9 1510.14  5828.7 1510.86  5835.4 1512.20  5840.9 1511.32  5872.7 1512.60
#Mann=5,-1,0
  4706.7    0.05       0  4723.6    0.12       0  4946.3    0.05       0
  4995.3    0.03       0  5004.8    0.05       0
Bank Sta=4995.3,5004.8
Exp/Cntr=0.3,0.1

Type RM Length L Ch R = 1,16500,500,500,500
BEGIN DESCRIPTION:
LEFT HAND CREEK 33.0
END DESCRIPTION:
XS GIS Cut Line= 3
      2749755.70     10167953.14      2750153.39     10168674.59
      2751105.67     10169453.10
#Sta/Elev= 30
  4176.2 1496.09  4189.9 1496.29  4227.8 1493.73  4461.6 1484.69  4662.2 1479.59
  4874.3 1478.05  4933.9 1475.79  4955.7 1474.12  4964.1 1472.48  4986.9 1471.44
  4987.6 1470.41  4988.1 1469.91  4999.4 1470.41  5015.4 1473.07  5028.8 1477.23
  5057.0 1479.38  5341.3 1480.08  5370.0 1481.43  5384.4 1480.91  5491.3 1483.19
  5512.2 1484.45  5576.0 1484.99  5661.7 1487.76  5938.6 1493.03  5952.9 1494.41
  6080.7 1499.68  6115.9 1502.36  6130.2 1504.65  6159.0 1503.24  6230.0 1508.43
#Mann=3,-1,0
  4176.2    0.05       0  4987.6    0.03       0  4999.4    0.05       0
Bank Sta=4987.6,4999.4
Exp/Cntr=0.3,0.1

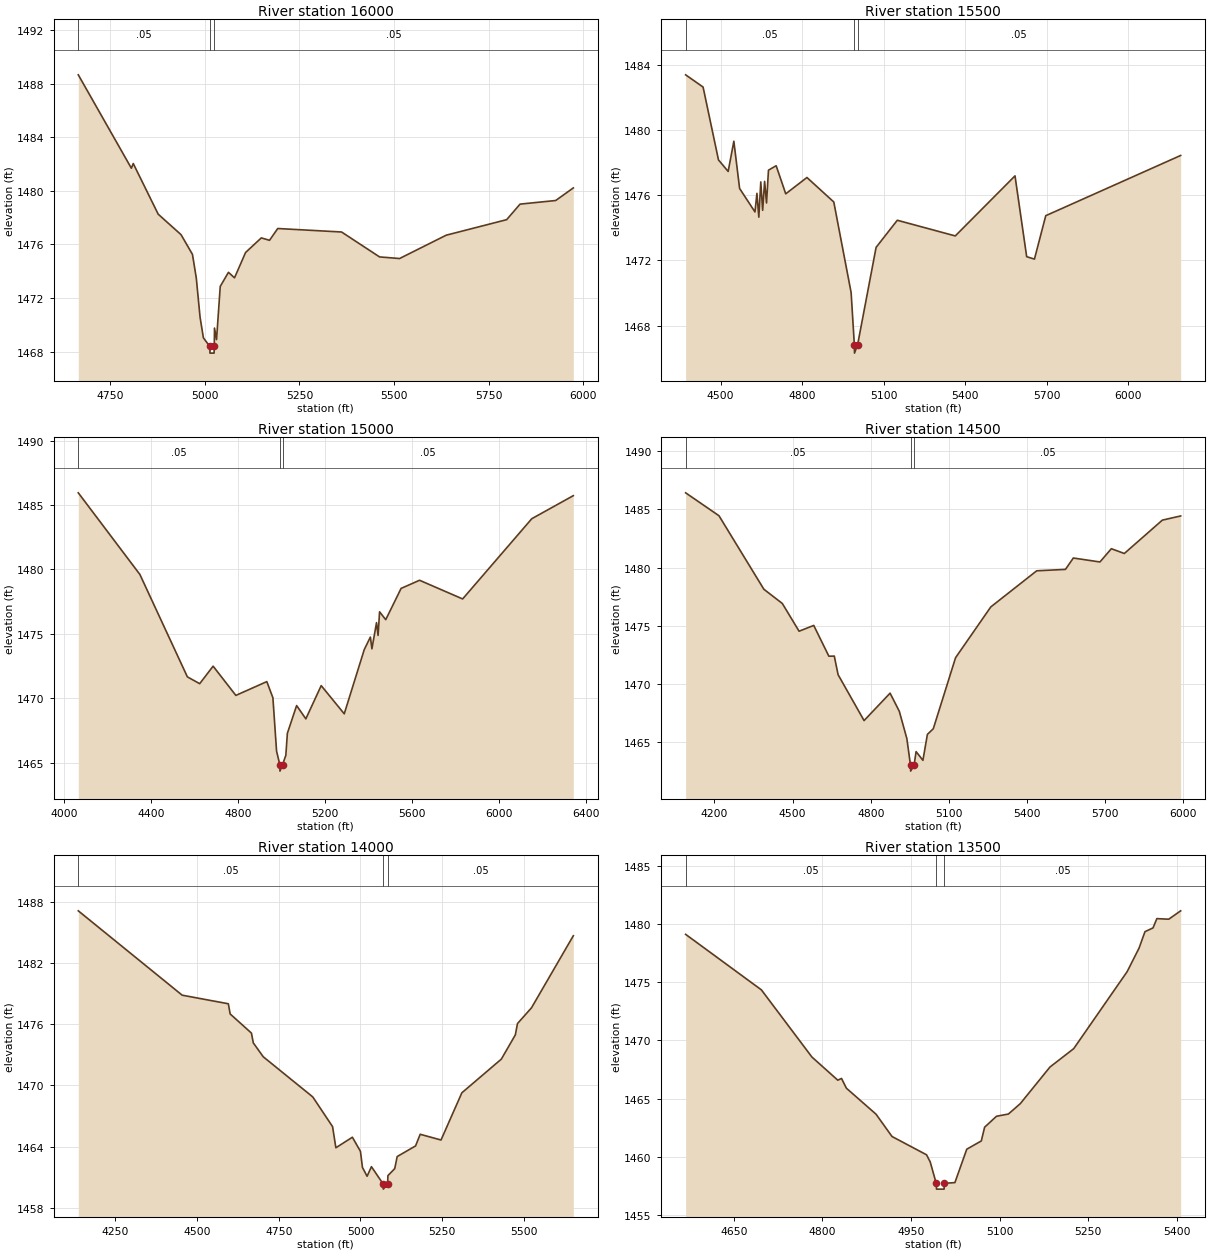
Type RM Length L Ch R = 1,16000,500,500,500
BEGIN DESCRIPTION:
LEFT HAND CREEK 32.0
END DESCRIPTION:
XS GIS Cut Line= 3
      2749655.68     10168203.10      2749690.37     10168535.60
      2750067.98     10169432.77
#Sta/Elev= 30
  4665.7 1488.66  4805.9 1481.69  4810.9 1482.04  4876.8 1478.26  4937.2 1476.73
  4967.3 1475.26  4977.4 1473.50  4987.4 1470.57  4996.2 1469.03  5013.1 1468.39
  5013.6 1467.89  5024.4 1467.89  5024.9 1468.39  5025.5 1469.76  5030.9 1468.90
  5040.7 1472.87  5062.4 1473.92  5078.4 1473.51  5107.6 1475.40  5149.2 1476.49
  5170.9 1476.31  5192.6 1477.19  5361.2 1476.93  5461.6 1475.07  5514.5 1474.95
  5637.4 1476.69  5797.3 1477.85  5832.7 1479.01  5926.9 1479.28  5973.4 1480.22
#Mann=3,-1,0
  4665.7    0.05       0  5013.1    0.05       0  5024.9    0.05       0
Bank Sta=5013.1,5024.9
Exp/Cntr=0.3,0.1

Type RM Length L Ch R = 1,15500,500,500,500
BEGIN DESCRIPTION:
LEFT HAND CREEK 31.0
END DESCRIPTION:
XS GIS Cut Line= 3
      2748762.40     10168085.52      2749215.93     10168520.34
      2749984.66     10169432.78
#Sta/Elev= 30
  4371.7 1483.37  4435.9 1482.62  4492.5 1478.16  4528.1 1477.45  4549.1 1479.30
  4570.2 1476.41  4626.8 1474.97  4634.0 1476.11  4641.0 1474.65  4648.2 1476.81
  4655.1 1475.07  4662.3 1476.84  4669.3 1475.52  4676.5 1477.53  4704.8 1477.80
  4740.0 1476.08  4818.0 1477.08  4916.8 1475.58  4980.6 1470.03  4992.5 1466.82
  4993.0 1466.32  5004.3 1466.82  5072.5 1472.80  5150.5 1474.46  5363.8 1473.50
  5583.6 1477.18  5626.5 1472.23  5655.1 1472.08  5696.7 1474.74  6193.1 1478.43
#Mann=3,-1,0
  4371.7    0.05       0  4992.5    0.05       0  5004.3    0.05       0
Bank Sta=4992.5,5004.3
Exp/Cntr=0.3,0.1

Type RM Length L Ch R = 1,15000,500,500,500
BEGIN DESCRIPTION:
LEFT HAND CREEK 30.0
END DESCRIPTION:
XS GIS Cut Line= 3
      2748205.69     10168553.12      2749044.84     10168967.08
      2750005.68     10169903.11
#Sta/Elev= 30
  4064.3 1485.95  4347.7 1479.61  4566.1 1471.66  4622.7 1471.13  4684.5 1472.49
  4789.1 1470.22  4931.5 1471.29  4959.5 1470.04  4976.4 1465.89  4991.4 1464.84
  4991.9 1464.34  5003.9 1464.84  5019.0 1465.57  5026.1 1467.28  5068.6 1469.43
  5111.0 1468.40  5181.7 1470.98  5287.7 1468.79  5379.6 1473.77  5407.9 1474.75
  5415.0 1473.84  5436.2 1475.87  5443.3 1474.88  5450.3 1476.71  5478.6 1476.10
  5549.3 1478.53  5634.2 1479.16  5832.3 1477.71  6150.4 1483.94  6341.4 1485.73
#Mann=3,-1,0
  4064.3    0.05       0  4991.4    0.05       0  5003.9    0.05       0
Bank Sta=4991.4,5003.9
Exp/Cntr=0.3,0.1

Type RM Length L Ch R = 1,14500,500,500,500
BEGIN DESCRIPTION:
LEFT HAND CREEK 29.0
END DESCRIPTION:
XS GIS Cut Line= 3
      2748155.69     10168553.11      2748708.05     10169277.05
      2749055.70     10170203.15
#Sta/Elev= 30
  4089.4 1486.43  4217.3 1484.46  4389.7 1478.13  4460.4 1476.91  4524.8 1474.52
  4581.0 1475.02  4639.1 1472.37  4659.9 1472.38  4674.5 1470.78  4774.2 1466.83
  4874.0 1469.19  4909.4 1467.63  4938.4 1465.28  4952.4 1462.98  4952.9 1462.48
  4966.0 1462.98  4973.8 1464.16  5000.0 1463.41  5017.2 1465.64  5039.9 1466.13
  5125.3 1472.24  5260.5 1476.61  5436.7 1479.72  5547.0 1479.84  5577.3 1480.82
  5679.4 1480.48  5723.2 1481.62  5773.0 1481.21  5918.9 1484.08  5989.2 1484.44
#Mann=3,-1,0
  4089.4    0.05       0  4952.4    0.05       0  4966.0    0.05       0
Bank Sta=4952.4,4966
Exp/Cntr=0.3,0.1

Type RM Length L Ch R = 1,14000,500,500,500
BEGIN DESCRIPTION:
LEFT HAND CREEK 28.0
END DESCRIPTION:
XS GIS Cut Line= 3
      2748105.68     10168553.08      2748228.08     10169407.55
      2747805.65     10169903.15
#Sta/Elev= 30
  4136.8 1487.09  4454.6 1478.83  4595.8 1477.99  4601.5 1476.99  4666.5 1475.12
  4672.2 1474.16  4702.6 1472.80  4854.1 1468.87  4914.7 1465.96  4924.8 1463.89
  4975.3 1464.92  5000.0 1463.54  5006.1 1461.97  5020.3 1461.10  5033.6 1462.04
  5069.5 1460.34  5070.0 1459.84  5083.2 1460.34  5084.0 1461.16  5104.9 1461.85
  5112.4 1463.03  5168.6 1464.07  5182.8 1465.21  5246.5 1464.65  5310.2 1469.27
  5431.0 1472.57  5473.8 1474.94  5480.4 1476.05  5523.2 1477.59  5651.2 1484.65
#Mann=3,-1,0
  4136.8    0.05       0  5069.5    0.05       0  5083.2    0.05       0
Bank Sta=5069.5,5083.2
Exp/Cntr=0.3,0.1

Type RM Length L Ch R = 1,13500,500,500,500
BEGIN DESCRIPTION:
LEFT HAND CREEK 27.0
END DESCRIPTION:
XS GIS Cut Line= 3
      2748055.69     10168953.10      2747797.75     10169299.14
      2747755.68     10169703.15
#Sta/Elev= 30
  4568.4 1479.11  4696.6 1474.34  4782.1 1468.57  4825.9 1466.58  4832.2 1466.73
  4840.5 1465.89  4890.6 1463.66  4917.7 1461.74  4976.1 1460.17  4982.3 1459.56
  4992.5 1457.72  4993.0 1457.22  5005.8 1457.22  5006.3 1457.72  5024.1 1457.78
  5044.2 1460.65  5068.8 1461.36  5074.4 1462.54  5094.5 1463.48  5114.6 1463.67
  5134.7 1464.56  5185.0 1467.71  5225.2 1469.29  5315.7 1475.91  5335.8 1477.93
  5345.8 1479.34  5359.4 1479.66  5365.9 1480.46  5386.0 1480.41  5406.2 1481.13
#Mann=3,-1,0
  4568.4    0.05       0  4992.5    0.05       0  5006.3    0.05       0
Bank Sta=4992.5,5006.3
Exp/Cntr=0.3,0.1

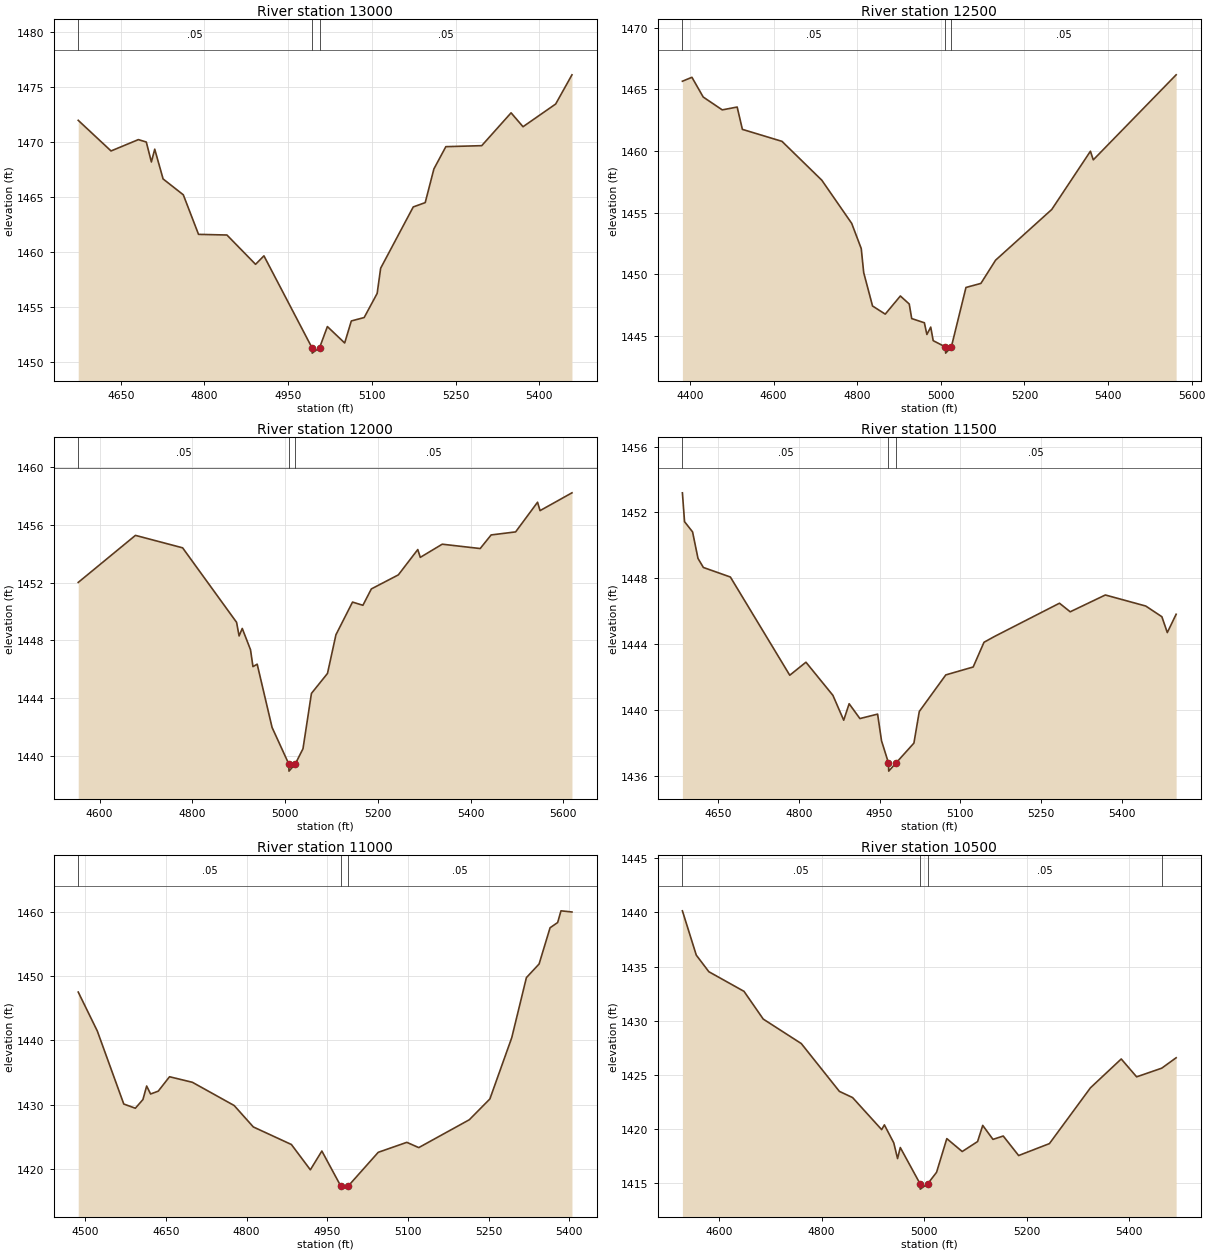
Type RM Length L Ch R = 1,13000,500,500,500
BEGIN DESCRIPTION:
LEFT HAND CREEK 26.0
END DESCRIPTION:
XS GIS Cut Line= 3
      2747555.70     10168853.08      2747321.25     10169209.00
      2747555.70     10169603.14
#Sta/Elev= 30
  4573.8 1471.97  4632.6 1469.19  4681.6 1470.22  4695.8 1470.00  4704.9 1468.19
  4710.9 1469.35  4725.9 1466.65  4762.1 1465.21  4789.4 1461.62  4840.3 1461.56
  4891.6 1458.90  4906.6 1459.67  4992.6 1451.34  4993.1 1450.84  5006.4 1451.34
  5020.3 1453.25  5051.3 1451.76  5063.2 1453.76  5086.2 1454.07  5109.5 1456.26
  5115.8 1458.55  5174.2 1464.11  5195.6 1464.50  5211.2 1467.56  5232.6 1469.58
  5296.9 1469.67  5349.5 1472.65  5370.9 1471.39  5429.4 1473.45  5458.6 1476.10
#Mann=3,-1,0
  4573.8    0.05       0  4992.6    0.05       0  5006.4    0.05       0
Bank Sta=4992.6,5006.4
Exp/Cntr=0.3,0.1

Type RM Length L Ch R = 1,12500,500,500,500
BEGIN DESCRIPTION:
LEFT HAND CREEK 25.0
END DESCRIPTION:
XS GIS Cut Line= 3
      2746355.66     10169003.10      2746874.65     10169338.80
      2747255.69     10169753.12
#Sta/Elev= 30
  4381.9 1465.65  4404.7 1465.97  4431.7 1464.37  4477.2 1463.33  4512.9 1463.56
  4525.4 1461.75  4620.1 1460.78  4715.4 1457.63  4786.9 1454.13  4809.7 1452.09
  4815.6 1450.14  4836.7 1447.44  4867.1 1446.78  4903.3 1448.25  4924.5 1447.60
  4930.4 1446.42  4960.7 1446.08  4966.7 1445.13  4975.9 1445.73  4981.8 1444.63
  5011.1 1444.12  5011.6 1443.62  5025.2 1444.12  5060.2 1448.94  5095.9 1449.27
  5131.0 1451.15  5265.4 1455.26  5357.9 1459.98  5364.7 1459.28  5562.9 1466.17
#Mann=3,-1,0
  4381.9    0.05       0  5011.1    0.05       0  5025.2    0.05       0
Bank Sta=5011.1,5025.2
Exp/Cntr=0.3,0.1

Type RM Length L Ch R = 1,12000,500,500,500
BEGIN DESCRIPTION:
LEFT HAND CREEK 24.0
END DESCRIPTION:
XS GIS Cut Line= 3
      2746095.75     10169453.59      2746511.66     10169614.34
      2747081.27     10169856.12
#Sta/Elev= 30
  4554.1 1452.01  4677.5 1455.26  4779.2 1454.40  4895.6 1449.25  4901.0 1448.31
  4907.8 1448.83  4925.6 1447.36  4930.9 1446.19  4940.0 1446.36  4972.1 1441.99
  5008.1 1439.47  5008.6 1438.97  5022.3 1439.47  5038.8 1440.52  5057.0 1444.34
  5091.6 1445.72  5109.8 1448.39  5145.6 1450.65  5168.0 1450.43  5186.2 1451.56
  5244.4 1452.53  5286.3 1454.28  5291.7 1453.74  5339.0 1454.65  5420.9 1454.35
  5444.5 1455.29  5497.3 1455.50  5544.6 1457.55  5550.0 1456.97  5618.8 1458.20
#Mann=3,-1,0
  4554.1    0.05       0  5008.1    0.05       0  5022.3    0.05       0
Bank Sta=5008.1,5022.3
Exp/Cntr=0.3,0.1

Type RM Length L Ch R = 1,11500,500,500,500
BEGIN DESCRIPTION:
LEFT HAND CREEK 23.0
END DESCRIPTION:
XS GIS Cut Line= 3
      2746206.83     10170057.76      2746621.95     10170092.83
      2747122.08     10170127.11
#Sta/Elev= 30
  4583.4 1453.19  4587.4 1451.44  4602.3 1450.82  4612.4 1449.21  4622.4 1448.66
  4672.6 1448.08  4783.0 1442.12  4813.1 1442.91  4863.2 1440.90  4883.3 1439.39
  4893.4 1440.39  4913.4 1439.49  4946.3 1439.76  4953.6 1438.14  4966.5 1436.80
  4967.0 1436.30  4980.7 1436.80  5013.8 1438.00  5023.8 1439.92  5073.1 1442.14
  5124.0 1442.62  5144.1 1444.12  5164.1 1444.48  5284.4 1446.49  5304.4 1445.97
  5369.7 1446.99  5444.8 1446.32  5474.8 1445.67  5484.9 1444.71  5501.3 1445.82
#Mann=3,-1,0
  4583.4    0.05       0  4966.5    0.05       0  4980.7    0.05       0
Bank Sta=4966.5,4980.7
Exp/Cntr=0.3,0.1

Type RM Length L Ch R = 1,11000,500,500,500
BEGIN DESCRIPTION:
LEFT HAND CREEK 22.0
END DESCRIPTION:
XS GIS Cut Line= 3
      2746305.70     10170203.13      2746657.62     10170576.39
      2747055.73     10170503.10
#Sta/Elev= 30
  4487.0 1447.51  4522.4 1441.47  4571.7 1430.11  4593.2 1429.46  4607.3 1430.81
  4614.2 1432.91  4621.5 1431.67  4635.7 1432.11  4656.7 1434.35  4699.2 1433.49
  4776.9 1429.88  4812.5 1426.55  4883.3 1423.82  4918.5 1419.89  4939.9 1422.81
  4974.9 1417.39  4975.4 1416.89  4989.1 1417.39  5044.7 1422.61  5097.8 1424.16
  5120.0 1423.34  5214.0 1427.67  5252.2 1430.90  5292.9 1440.43  5320.1 1449.75
  5343.7 1451.87  5364.1 1457.50  5378.2 1458.31  5384.4 1460.13  5404.8 1459.95
#Mann=3,-1,0
  4487.0    0.05       0  4974.9    0.05       0  4989.1    0.05       0
Bank Sta=4974.9,4989.1
Exp/Cntr=0.3,0.1

Type RM Length L Ch R = 1,10500,500,500,500
BEGIN DESCRIPTION:
LEFT HAND CREEK 21.0
END DESCRIPTION:
XS GIS Cut Line= 3
      2746061.02     10170224.40      2746217.22     10170669.06
      2746206.91     10171160.05
#Sta/Elev= 30
  4528.7 1440.15  4555.8 1436.06  4580.3 1434.53  4648.8 1432.72  4686.3 1430.16
  4760.5 1427.90  4834.7 1423.49  4860.4 1422.92  4917.1 1419.96  4922.4 1420.40
  4940.7 1418.74  4948.1 1417.29  4953.4 1418.31  4991.9 1414.97  4992.4 1414.47
  5007.0 1414.97  5024.1 1416.02  5044.1 1419.13  5074.1 1417.94  5104.1 1418.86
  5114.1 1420.35  5134.1 1419.06  5154.1 1419.37  5184.1 1417.57  5244.1 1418.67
  5324.1 1423.82  5384.1 1426.48  5414.1 1424.83  5463.0 1425.63  5491.1 1426.59
#Mann=4,-1,0
  4528.7    0.05       0  4991.9    0.05       0  5007.0    0.05       0
  5463.0    0.12       0
Bank Sta=4991.9,5007
Exp/Cntr=0.3,0.1

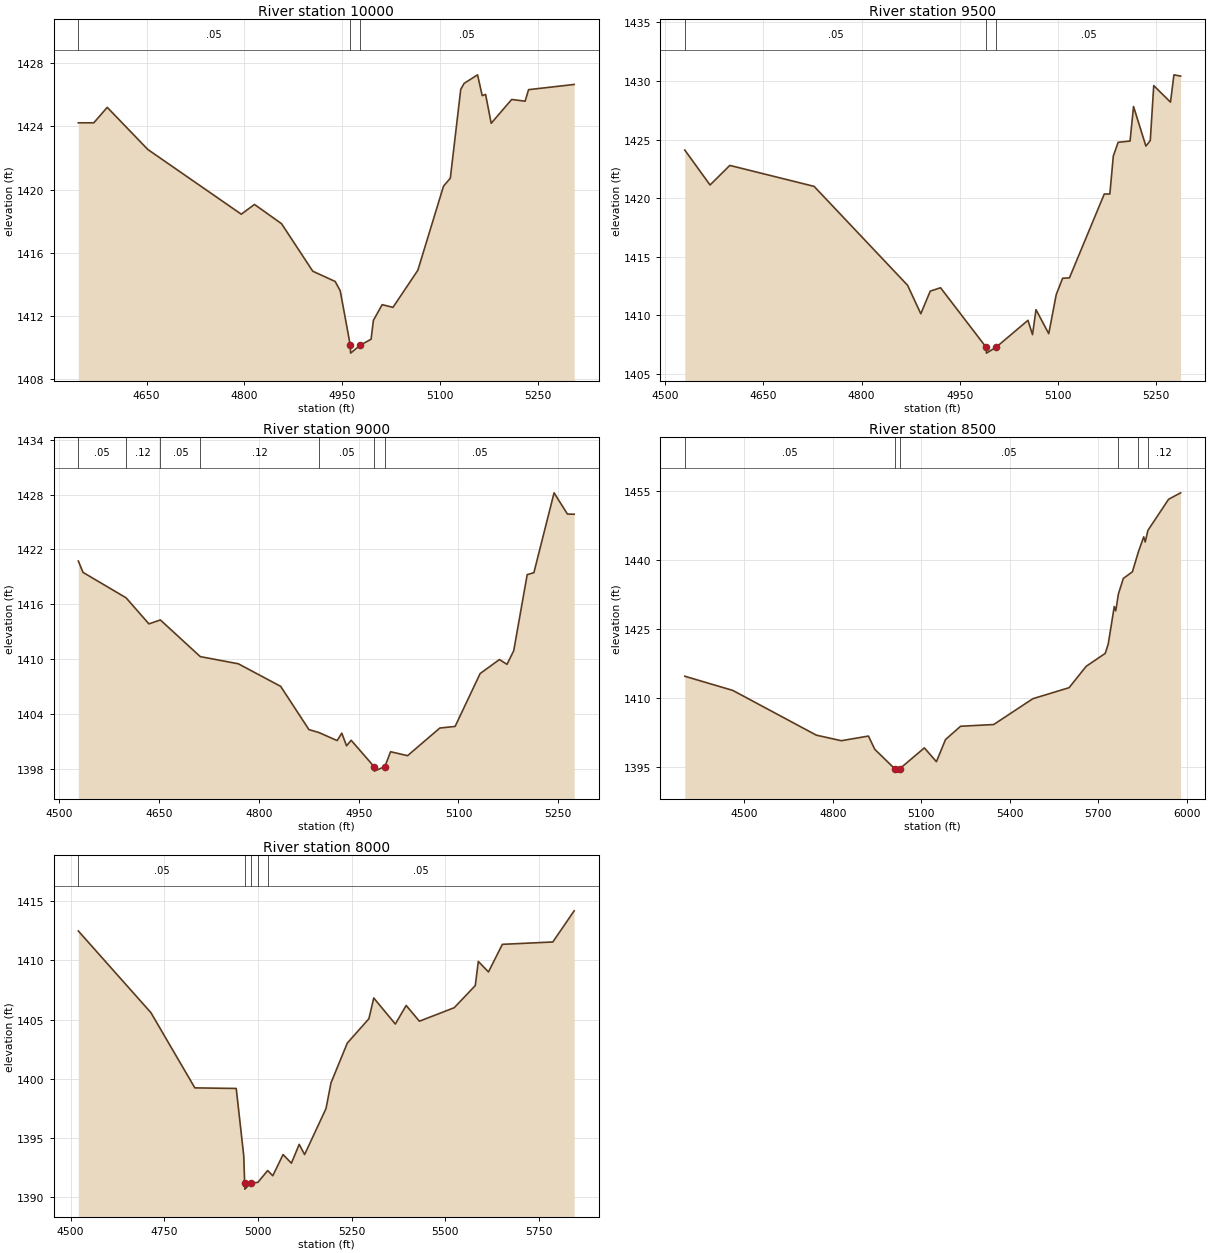
Type RM Length L Ch R = 1,10000,500,500,500
BEGIN DESCRIPTION:
LEFT HAND CREEK 20.0
END DESCRIPTION:
XS GIS Cut Line= 3
      2745894.36     10170280.03      2745789.03     10170722.26
      2745700.31     10171014.81
#Sta/Elev= 30
  4545.4 1424.23  4569.1 1424.23  4589.7 1425.21  4652.0 1422.54  4795.3 1418.44
  4815.5 1419.06  4857.0 1417.84  4904.9 1414.83  4939.2 1414.18  4947.0 1413.59
  4962.4 1410.14  4962.9 1409.64  4977.6 1410.14  4994.3 1410.52  4997.9 1411.72
  5011.3 1412.71  5027.9 1412.54  5066.0 1414.89  5105.4 1420.22  5115.8 1420.72
  5131.8 1426.35  5137.0 1426.73  5157.6 1427.27  5164.7 1425.95  5169.9 1426.03
  5178.5 1424.20  5209.9 1425.71  5230.5 1425.60  5235.8 1426.33  5305.7 1426.66
#Mann=3,-1,0
  4545.4    0.05       0  4962.4    0.03       0  4977.6    0.05       0
Bank Sta=4962.4,4977.6
Exp/Cntr=0.3,0.1

Type RM Length L Ch R = 1,9500,500,500,500
BEGIN DESCRIPTION:
LEFT HAND CREEK 19.0
END DESCRIPTION:
XS GIS Cut Line= 3
      2745463.81     10170064.75      2745409.67     10170531.82
      2745505.69     10170803.13
#Sta/Elev= 30
  4529.8 1424.10  4568.4 1421.12  4598.6 1422.79  4727.5 1421.00  4870.4 1412.56
  4890.6 1410.13  4905.0 1412.06  4920.8 1412.35  4990.5 1407.27  4991.0 1406.77
  5005.7 1407.27  5054.4 1409.57  5061.4 1408.35  5066.7 1410.48  5086.2 1408.43
  5097.6 1411.76  5107.4 1413.16  5117.8 1413.19  5171.1 1420.35  5179.6 1420.35
  5184.9 1423.59  5192.3 1424.76  5210.5 1424.87  5215.8 1427.82  5234.7 1424.44
  5241.4 1424.91  5246.7 1429.60  5272.3 1428.19  5277.6 1430.52  5287.8 1430.41
#Mann=3,-1,0
  4529.8    0.05       0  4990.5    0.05       0  5005.7    0.05       0
Bank Sta=4990.5,5005.7
Exp/Cntr=0.3,0.1

Type RM Length L Ch R = 1,9000,500,500,500
BEGIN DESCRIPTION:
LEFT HAND CREEK 18.0
END DESCRIPTION:
XS GIS Cut Line= 3
      2744805.70     10170603.13      2745134.36     10170940.92
      2745405.64     10170903.12
#Sta/Elev= 30
  4528.7 1420.73  4535.8 1419.49  4600.5 1416.71  4634.8 1413.86  4652.0 1414.29
  4712.0 1410.28  4769.1 1409.50  4832.8 1407.03  4875.3 1402.30  4890.3 1401.98
  4917.7 1401.10  4924.7 1401.91  4931.8 1400.53  4938.8 1401.13  4973.1 1398.26
  4973.6 1397.76  4989.4 1398.26  4998.0 1399.88  5023.5 1399.45  5072.0 1402.47
  5095.0 1402.65  5132.6 1408.43  5161.6 1409.96  5173.0 1409.44  5183.1 1410.93
  5203.3 1419.24  5213.4 1419.46  5243.7 1428.19  5263.8 1425.87  5273.9 1425.85
#Mann=7,-1,0
  4528.7    0.05       0  4600.5    0.12       0  4652.0    0.05       0
  4712.0    0.12       0  4890.3    0.05       0  4973.1    0.05       0
  4989.4    0.05       0
Bank Sta=4973.1,4989.4
Exp/Cntr=0.3,0.1

Type RM Length L Ch R = 1,8500,500,500,500
BEGIN DESCRIPTION:
LEFT HAND CREEK 17.0
END DESCRIPTION:
XS GIS Cut Line= 3
      2744305.66     10170803.09      2744797.54     10171302.97
      2745755.66     10171503.11
#Sta/Elev= 30
  4298.7 1414.64  4461.4 1411.56  4744.3 1401.84  4829.1 1400.63  4921.0 1401.64
  4942.3 1398.77  5010.4 1394.52  5010.9 1394.02  5026.7 1394.52  5110.5 1399.07
  5151.3 1396.07  5182.0 1400.87  5233.1 1403.77  5345.4 1404.15  5478.2 1409.76
  5600.8 1412.15  5659.0 1416.81  5723.4 1419.61  5733.6 1421.66  5753.9 1429.78
  5759.0 1428.85  5768.0 1432.53  5784.7 1435.90  5815.4 1437.34  5835.7 1441.67
  5853.8 1444.94  5858.9 1443.82  5867.9 1446.33  5938.0 1453.10  5978.8 1454.50
#Mann=6,-1,0
  4298.7    0.05       0  5010.4    0.05       0  5026.7    0.05       0
  5768.0    0.12       0  5835.7    0.05       0  5867.9    0.12       0
Bank Sta=5010.4,5026.7
Exp/Cntr=0.3,0.1

Type RM Length L Ch R = 1,8000,500,500,500
BEGIN DESCRIPTION:
LEFT HAND CREEK 16.0
END DESCRIPTION:
XS GIS Cut Line= 3
      2744305.69     10170953.14      2744343.17     10171431.07
      2745005.70     10171953.12
#Sta/Elev= 30
  4520.6 1412.49  4714.3 1405.59  4831.5 1399.24  4941.9 1399.19  4961.9 1393.52
  4964.4 1391.19  4964.9 1390.69  4980.9 1391.19  4999.6 1391.26  5025.8 1392.26
  5039.4 1391.82  5066.9 1393.61  5089.1 1392.88  5109.9 1394.47  5124.3 1393.61
  5181.4 1397.49  5194.8 1399.67  5238.2 1403.02  5295.9 1405.08  5308.8 1406.83
  5366.4 1404.63  5395.3 1406.20  5430.6 1404.87  5523.6 1406.01  5579.7 1407.88
  5587.8 1409.92  5614.9 1409.03  5651.9 1411.36  5786.6 1411.56  5843.5 1414.19
#Mann=5,-1,0
  4520.6    0.05       0  4964.4    0.07       0  4980.9    0.05       0
  4999.6    0.12       0  5025.8    0.05       0
Bank Sta=4964.4,4980.9
Exp/Cntr=0.3,0.1