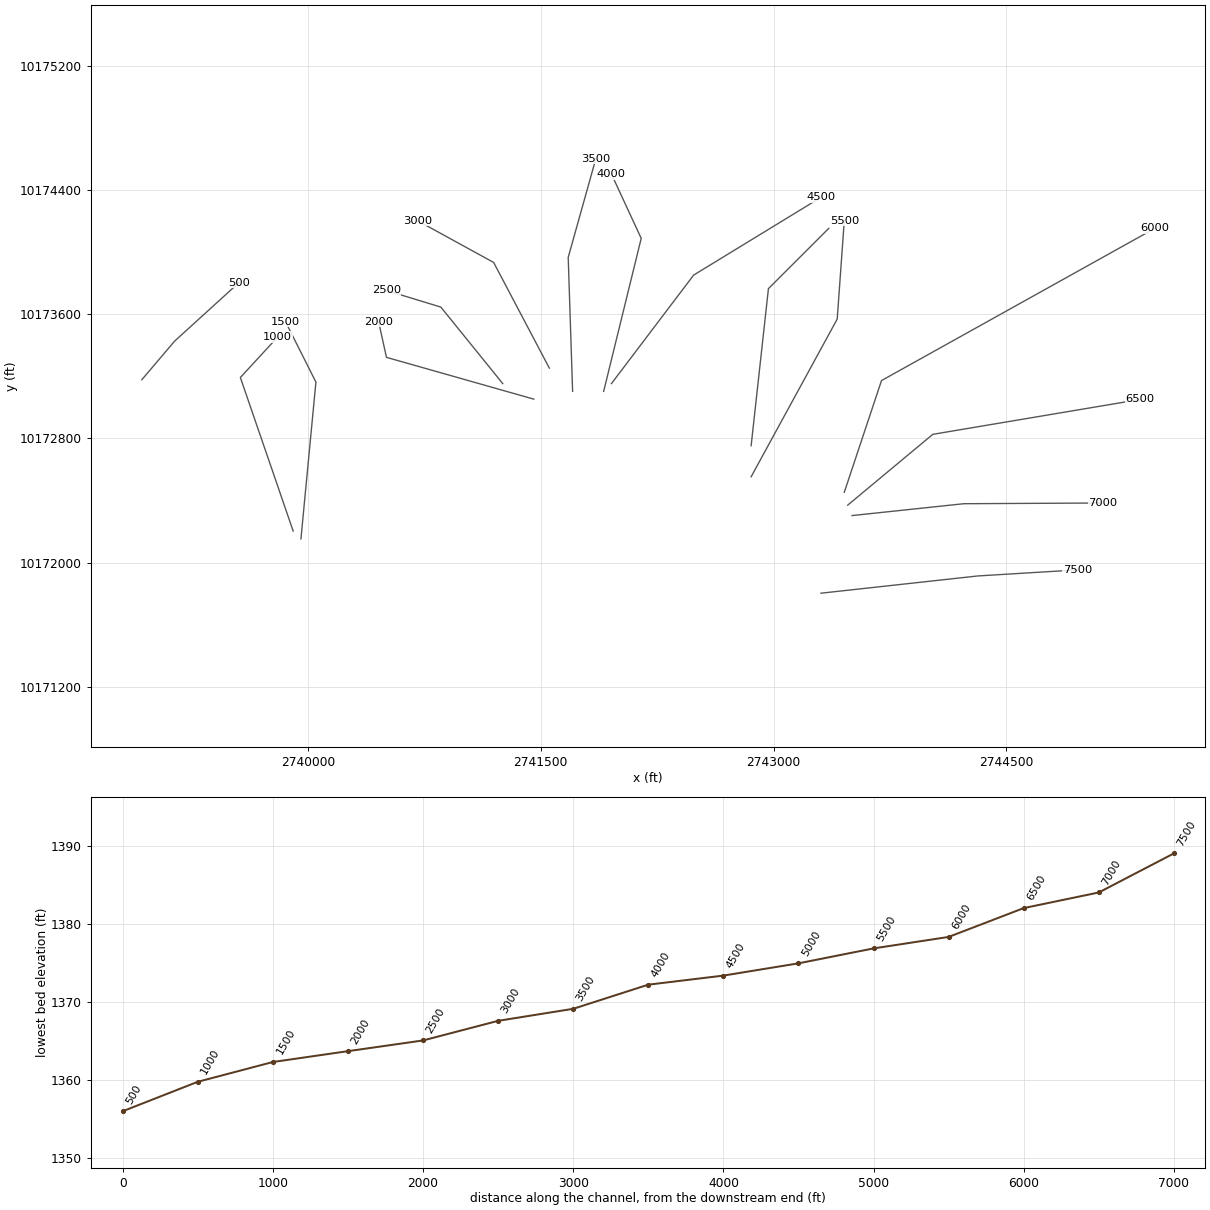
HEC-RAS study LEFT HAND CREEK.prj: LEFT HAND CREEK Base Level Engineering

--- LEFT HAND CREEK.g01 (geometry) --- (continued)

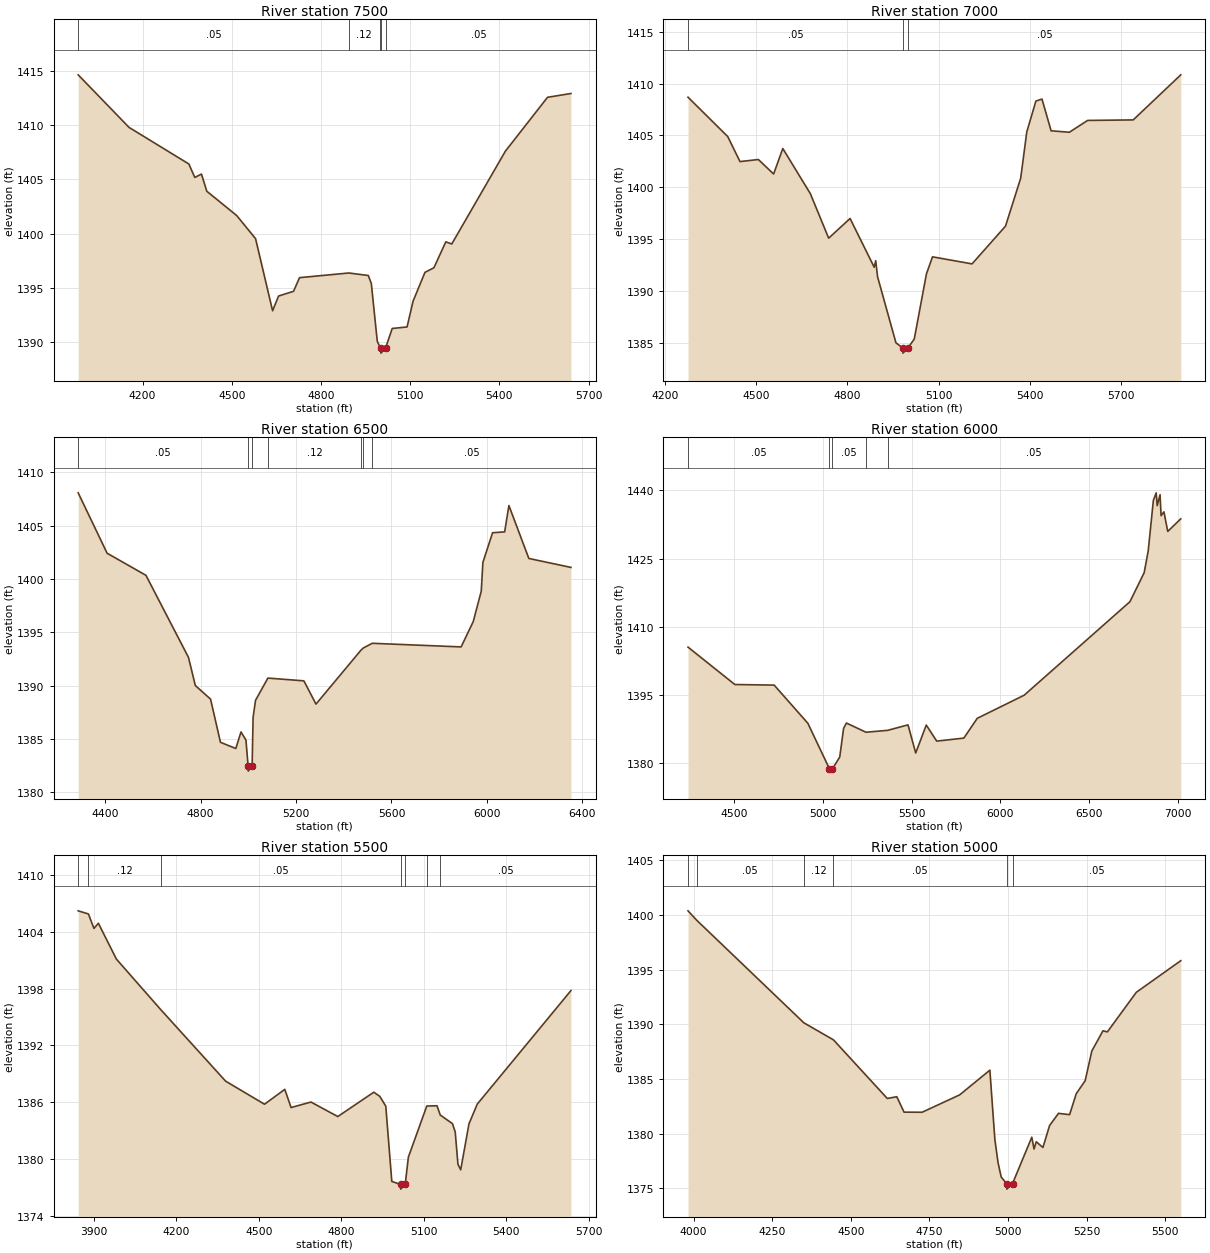
Type RM Length L Ch R = 1,7500,500,500,500
BEGIN DESCRIPTION:
LEFT HAND CREEK 15.0
END DESCRIPTION:
XS GIS Cut Line= 3
      2743305.69     10171803.11      2744316.10     10171914.18
      2744955.72     10171953.11
#Sta/Elev= 30
  3983.5 1414.62  4154.5 1409.78  4355.7 1406.41  4375.8 1405.17  4398.2 1405.48
  4416.1 1403.90  4516.7 1401.66  4580.2 1399.53  4637.4 1392.89  4657.5 1394.25
  4707.8 1394.68  4728.0 1395.94  4893.8 1396.37  4959.3 1396.14  4969.4 1395.41
  4989.5 1390.08  4998.2 1389.57  5001.3 1389.49  5001.8 1388.99  5017.8 1389.49
  5039.7 1391.26  5089.7 1391.40  5109.8 1393.77  5149.9 1396.43  5179.9 1396.85
  5220.0 1399.24  5240.0 1399.04  5420.4 1407.59  5562.1 1412.55  5640.8 1412.90
#Mann=5,-1,0
  3983.5    0.05       0  4893.8    0.12       0  4998.2    0.05       0
  5001.3    0.05       0  5017.8    0.05       0
Bank Sta=5001.3,5017.8
Exp/Cntr=0.3,0.1

Type RM Length L Ch R = 1,7000,500,500,500
BEGIN DESCRIPTION:
LEFT HAND CREEK 14.0
END DESCRIPTION:
XS GIS Cut Line= 3
      2743505.72     10172303.12      2744225.38     10172379.48
      2745122.06     10172384.14
#Sta/Elev= 30
  4276.3 1408.68  4407.0 1404.88  4447.2 1402.47  4507.6 1402.67  4557.8 1401.27
  4588.0 1403.73  4678.5 1399.38  4738.8 1395.08  4809.2 1396.98  4888.5 1392.28
  4893.5 1392.91  4899.7 1391.35  4960.1 1384.98  4982.7 1384.49  4983.2 1383.99
  4999.6 1384.49  5020.3 1385.35  5060.3 1391.63  5080.3 1393.28  5210.3 1392.60
  5320.3 1396.24  5370.3 1400.87  5390.3 1405.33  5420.3 1408.31  5440.3 1408.50
  5470.3 1405.44  5530.3 1405.30  5590.3 1406.44  5740.3 1406.49  5896.7 1410.84
#Mann=3,-1,0
  4276.3    0.05       0  4982.7    0.05       0  4999.6    0.05       0
Bank Sta=4982.7,4999.6
Exp/Cntr=0.3,0.1

Type RM Length L Ch R = 1,6500,500,500,500
BEGIN DESCRIPTION:
LEFT HAND CREEK 13.0
END DESCRIPTION:
XS GIS Cut Line= 3
      2743477.70     10172370.26      2744025.95     10172826.42
      2745359.60     10173050.81
#Sta/Elev= 30
  4286.8 1408.07  4408.1 1402.41  4570.9 1400.34  4749.2 1392.65  4777.9 1390.01
  4841.7 1388.74  4883.3 1384.69  4947.6 1384.11  4969.3 1385.66  4990.1 1384.90
  4999.1 1382.49  4999.6 1381.99  5016.0 1382.49  5020.0 1387.01  5030.2 1388.62
  5082.1 1390.71  5233.0 1390.45  5283.7 1388.27  5472.5 1393.33  5481.5 1393.52
  5519.6 1393.97  5892.1 1393.63  5942.8 1396.00  5976.4 1398.84  5983.4 1401.55
  6023.9 1404.33  6074.6 1404.41  6092.4 1406.88  6176.0 1401.92  6352.4 1401.08
#Mann=7,-1,0
  4286.8    0.05       0  4999.1    0.05       0  5016.0    0.05       0
  5082.1    0.12       0  5472.5    0.05       0  5481.5    0.12       0
  5519.6    0.05       0
Bank Sta=4999.1,5016
Exp/Cntr=0.3,0.1

Type RM Length L Ch R = 1,6000,500,500,500
BEGIN DESCRIPTION:
LEFT HAND CREEK 12.0
END DESCRIPTION:
XS GIS Cut Line= 3
      2743455.68     10172453.10      2743695.42     10173172.72
      2745455.71     10174153.12
#Sta/Elev= 30
  4241.5 1405.56  4505.0 1397.34  4726.4 1397.21  4916.1 1388.81  5037.6 1378.80
  5038.1 1378.30  5054.5 1378.80  5095.4 1381.40  5117.2 1387.72  5133.2 1388.87
  5243.0 1386.85  5365.5 1387.27  5479.6 1388.47  5523.0 1382.29  5582.4 1388.43
  5641.3 1384.90  5793.9 1385.56  5869.4 1389.91  6133.5 1394.99  6728.7 1415.54
  6808.8 1421.92  6831.7 1426.72  6860.5 1437.80  6876.5 1439.48  6882.3 1436.66
  6898.3 1439.07  6904.0 1434.46  6920.0 1435.30  6941.7 1431.00  7014.9 1433.77
#Mann=5,-1,0
  4241.5    0.05       0  5037.6    0.05       0  5054.5    0.05       0
  5243.0    0.12       0  5365.5    0.05       0
Bank Sta=5037.6,5054.5
Exp/Cntr=0.3,0.1

Type RM Length L Ch R = 1,5500,500,500,500
BEGIN DESCRIPTION:
LEFT HAND CREEK 11.0
END DESCRIPTION:
XS GIS Cut Line= 3
      2742855.69     10172553.13      2743410.13     10173568.97
      2743455.69     10174203.14
#Sta/Elev= 30
  3842.7 1406.20  3880.0 1405.87  3900.1 1404.34  3916.2 1404.89  3981.7 1401.11
  4143.6 1395.76  4379.4 1388.22  4520.8 1385.79  4594.6 1387.36  4617.4 1385.44
  4689.7 1386.02  4787.5 1384.49  4918.5 1387.06  4940.3 1386.62  4962.1 1385.58
  4984.0 1377.64  5015.7 1377.33  5016.2 1376.83  5032.7 1377.33  5044.3 1380.21
  5111.3 1385.60  5148.4 1385.63  5160.3 1384.65  5204.7 1383.74  5214.7 1382.87
  5224.7 1379.45  5234.7 1378.87  5264.8 1383.72  5294.9 1385.80  5635.8 1397.78
#Mann=7,-1,0
  3842.7    0.05       0  3880.0    0.12       0  4143.6    0.05       0
  5015.7    0.05       0  5032.7    0.05       0  5111.3    0.12       0
  5160.3    0.05       0
Bank Sta=5015.7,5032.7
Exp/Cntr=0.3,0.1

Type RM Length L Ch R = 1,5000,500,500,500
BEGIN DESCRIPTION:
LEFT HAND CREEK 10.0
END DESCRIPTION:
XS GIS Cut Line= 3
      2742855.68     10172753.12      2742967.11     10173764.90
      2743355.71     10174153.13
#Sta/Elev= 30
  3982.1 1400.37  4009.7 1399.51  4350.5 1390.13  4444.7 1388.57  4615.9 1383.21
  4646.1 1383.37  4669.2 1381.96  4726.6 1381.95  4846.1 1383.54  4942.1 1385.80
  4958.0 1379.47  4968.0 1377.36  4978.1 1376.03  4995.5 1375.42  4996.0 1374.92
  5014.1 1375.42  5075.5 1379.67  5082.6 1378.59  5089.7 1379.25  5110.9 1378.73
  5132.1 1380.74  5160.4 1381.85  5195.7 1381.73  5216.9 1383.65  5245.2 1384.83
  5266.4 1387.55  5301.8 1389.40  5315.9 1389.30  5407.9 1392.92  5549.3 1395.81
#Mann=6,-1,0
  3982.1    0.12       0  4009.7    0.05       0  4350.5    0.12       0
  4444.7    0.05       0  4995.5    0.05       0  5014.1    0.05       0
Bank Sta=4995.5,5014.1
Exp/Cntr=0.3,0.1

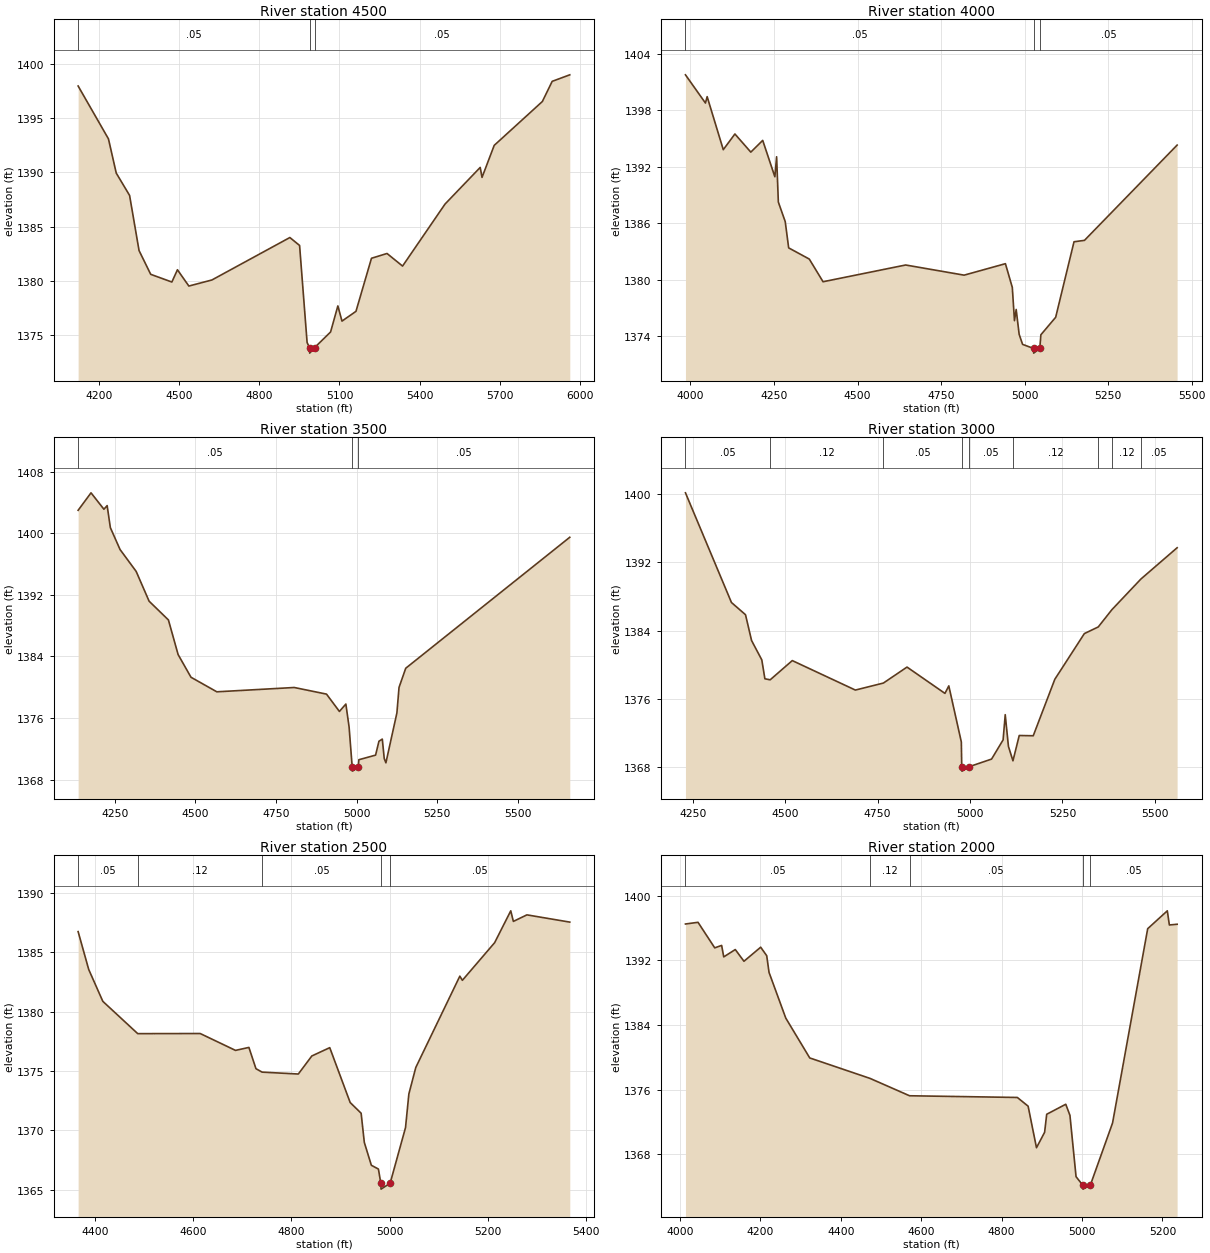
Type RM Length L Ch R = 1,4500,500,500,500
BEGIN DESCRIPTION:
LEFT HAND CREEK 9.0
END DESCRIPTION:
XS GIS Cut Line= 3
      2741955.71     10173153.15      2742485.34     10173852.16
      2743305.68     10174353.11
#Sta/Elev= 30
  4123.0 1397.96  4236.4 1393.09  4265.5 1389.94  4315.4 1387.88  4350.8 1382.80
  4394.4 1380.61  4473.5 1379.90  4494.3 1381.03  4537.0 1379.53  4623.3 1380.09
  4914.6 1384.00  4951.0 1383.27  4979.1 1374.33  4988.2 1373.85  4988.7 1373.35
  5006.8 1373.85  5066.9 1375.30  5094.1 1377.70  5109.5 1376.30  5161.8 1377.20
  5219.8 1382.09  5277.9 1382.53  5336.0 1381.37  5494.7 1387.08  5626.3 1390.46
  5633.1 1389.54  5678.6 1392.49  5858.6 1396.53  5895.4 1398.39  5961.2 1398.99
#Mann=3,-1,0
  4123.0    0.05       0  4988.2    0.03       0  5006.8    0.05       0
Bank Sta=4988.2,5006.8
Exp/Cntr=0.3,0.1

Type RM Length L Ch R = 1,4000,500,500,500
BEGIN DESCRIPTION:
LEFT HAND CREEK 8.0
END DESCRIPTION:
XS GIS Cut Line= 3
      2741905.69     10173103.14      2742147.57     10174088.80
      2741955.68     10174503.12
#Sta/Elev= 30
  3985.1 1401.78  4044.9 1398.78  4050.0 1399.46  4098.3 1393.82  4133.1 1395.49
  4180.7 1393.56  4216.3 1394.81  4252.7 1390.94  4257.9 1393.07  4263.1 1388.25
  4283.7 1386.17  4294.0 1383.38  4355.7 1382.19  4396.9 1379.78  4644.1 1381.56
  4819.1 1380.48  4942.7 1381.70  4963.3 1379.18  4969.8 1375.64  4974.9 1376.83
  4983.8 1374.19  4994.1 1373.12  5026.8 1372.69  5027.3 1372.19  5045.6 1372.69
  5048.8 1374.14  5093.1 1376.00  5148.0 1384.03  5179.3 1384.18  5456.6 1394.31
#Mann=3,-1,0
  3985.1    0.05       0  5026.8    0.05       0  5045.6    0.05       0
Bank Sta=5026.8,5045.6
Exp/Cntr=0.3,0.1

Type RM Length L Ch R = 1,3500,500,500,500
BEGIN DESCRIPTION:
LEFT HAND CREEK 7.0
END DESCRIPTION:
XS GIS Cut Line= 3
      2741705.68     10173103.16      2741677.34     10173966.29
      2741855.68     10174603.09
#Sta/Elev= 30
  4136.4 1402.97  4176.4 1405.24  4216.4 1403.11  4226.4 1403.58  4236.4 1400.72
  4266.4 1397.88  4316.5 1395.03  4356.5 1391.17  4416.5 1388.73  4446.5 1384.24
  4486.5 1381.29  4566.6 1379.40  4806.7 1379.96  4906.8 1379.10  4946.8 1376.85
  4966.8 1377.81  4976.8 1374.84  4986.5 1369.60  4987.0 1369.10  5005.3 1369.60
  5007.1 1370.58  5059.0 1371.18  5069.4 1372.98  5079.8 1373.26  5085.8 1370.74
  5091.0 1370.18  5125.1 1376.66  5131.7 1379.97  5152.5 1382.46  5661.3 1399.47
#Mann=3,-1,0
  4136.4    0.05       0  4986.5    0.05       0  5005.3    0.05       0
Bank Sta=4986.5,5005.3
Exp/Cntr=0.3,0.1

Type RM Length L Ch R = 1,3000,500,500,500
BEGIN DESCRIPTION:
LEFT HAND CREEK 6.0
END DESCRIPTION:
XS GIS Cut Line= 3
      2741555.70     10173253.07      2741196.94     10173933.71
      2740705.67     10174203.12
#Sta/Elev= 30
  4230.6 1400.14  4355.0 1387.30  4393.0 1385.87  4409.4 1382.85  4437.1 1380.58
  4445.4 1378.37  4459.7 1378.25  4519.5 1380.50  4690.1 1377.05  4765.9 1377.87
  4829.8 1379.74  4932.4 1376.66  4942.8 1377.54  4976.7 1370.97  4977.8 1368.06
  4978.3 1367.56  4996.6 1368.06  5058.5 1368.97  5089.7 1371.22  5095.4 1374.17
  5104.1 1370.45  5116.3 1368.77  5133.3 1371.73  5171.2 1371.70  5229.5 1378.31
  5309.4 1383.66  5347.0 1384.44  5383.9 1386.46  5462.4 1390.05  5560.3 1393.71
#Mann=9,-1,0
  4230.6    0.05       0  4459.7    0.12       0  4765.9    0.05       0
  4977.8    0.03       0  4996.6    0.05       0  5116.3    0.12       0
  5347.0    0.05       0  5383.9    0.12       0  5462.4    0.05       0
Bank Sta=4977.8,4996.6
Exp/Cntr=0.3,0.1

Type RM Length L Ch R = 1,2500,500,500,500
BEGIN DESCRIPTION:
LEFT HAND CREEK 5.0
END DESCRIPTION:
XS GIS Cut Line= 3
      2741255.67     10173153.13      2740856.71     10173646.24
      2740505.71     10173753.10
#Sta/Elev= 30
  4365.7 1386.73  4387.3 1383.54  4416.0 1380.86  4487.1 1378.14  4614.3 1378.15
  4686.2 1376.73  4713.5 1376.98  4727.8 1375.19  4740.3 1374.90  4814.1 1374.74
  4841.6 1376.26  4878.1 1376.96  4919.7 1372.34  4942.0 1371.44  4948.5 1368.98
  4962.8 1367.06  4977.2 1366.74  4982.1 1365.55  4982.6 1365.05  5001.1 1365.55
  5032.4 1370.23  5039.2 1373.06  5053.3 1375.29  5143.0 1382.98  5148.2 1382.63
  5213.9 1385.80  5246.7 1388.48  5252.0 1387.59  5279.6 1388.14  5366.9 1387.53
#Mann=5,-1,0
  4365.7    0.05       0  4487.1    0.12       0  4740.3    0.05       0
  4982.1    0.05       0  5001.1    0.05       0
Bank Sta=4982.1,5001.1
Exp/Cntr=0.3,0.1

Type RM Length L Ch R = 1,2000,500,500,500
BEGIN DESCRIPTION:
LEFT HAND CREEK 4.0
END DESCRIPTION:
XS GIS Cut Line= 3
      2741455.68     10173053.11      2740506.62     10173322.30
      2740455.68     10173553.15
#Sta/Elev= 30
  4013.5 1396.48  4044.7 1396.69  4086.3 1393.53  4103.5 1393.83  4108.7 1392.41
  4137.4 1393.32  4159.0 1391.87  4200.6 1393.61  4215.6 1392.56  4221.4 1390.49
  4263.0 1384.84  4322.6 1379.91  4472.5 1377.38  4570.9 1375.23  4839.0 1375.02
  4865.8 1373.94  4886.6 1368.80  4906.8 1370.71  4912.0 1372.94  4959.4 1374.18
  4969.8 1372.81  4985.0 1365.22  5001.5 1364.18  5002.0 1363.68  5020.6 1364.18
  5075.8 1371.86  5163.2 1395.90  5212.0 1398.11  5217.1 1396.36  5236.4 1396.45
#Mann=5,-1,0
  4013.5    0.05       0  4472.5    0.12       0  4570.9    0.05       0
  5001.5    0.03       0  5020.6    0.05       0
Bank Sta=5001.5,5020.6
Exp/Cntr=0.3,0.1

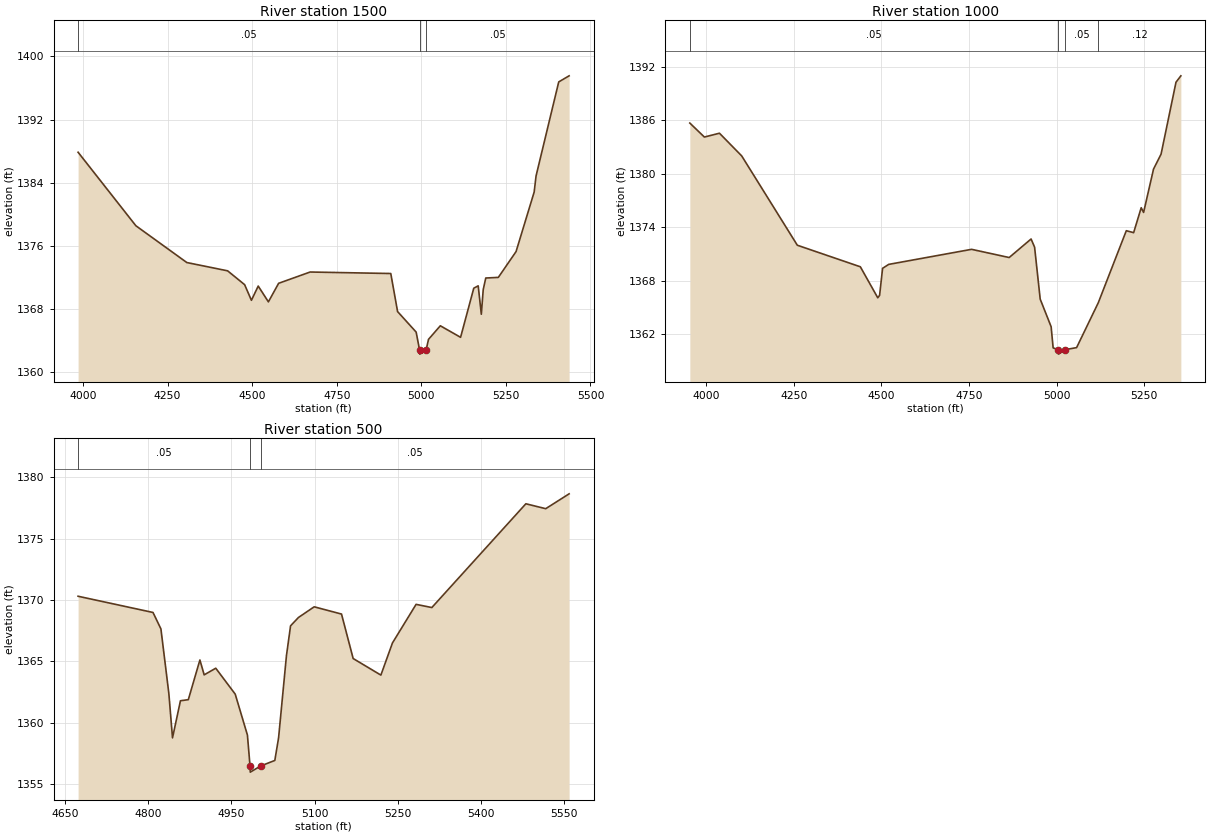
Type RM Length L Ch R = 1,1500,500,500,500
BEGIN DESCRIPTION:
LEFT HAND CREEK 3.0
END DESCRIPTION:
XS GIS Cut Line= 3
      2739955.69     10172153.12      2740052.15     10173162.93
      2739855.67     10173553.15
#Sta/Elev= 30
  3985.6 1387.86  4156.4 1378.55  4307.0 1373.89  4427.6 1372.84  4477.8 1371.09
  4497.9 1369.11  4518.0 1370.91  4548.1 1368.91  4578.3 1371.26  4671.4 1372.69
  4909.8 1372.50  4929.9 1367.68  4984.8 1365.08  4995.0 1362.79  4995.5 1362.29
  5014.1 1362.79  5021.3 1364.16  5056.2 1365.88  5116.1 1364.42  5155.1 1370.64
  5168.2 1370.94  5177.4 1367.34  5183.0 1370.45  5190.5 1371.93  5227.7 1372.01
  5280.1 1375.28  5333.6 1382.82  5339.2 1384.86  5406.2 1396.77  5436.9 1397.54
#Mann=3,-1,0
  3985.6    0.05       0  4995.0    0.05       0  5014.1    0.05       0
Bank Sta=4995,5014.1
Exp/Cntr=0.3,0.1

Type RM Length L Ch R = 1,1000,500,500,500
BEGIN DESCRIPTION:
LEFT HAND CREEK 2.0
END DESCRIPTION:
XS GIS Cut Line= 3
      2739905.67     10172203.16      2739565.48     10173192.50
      2739805.67     10173453.10
#Sta/Elev= 30
  3953.8 1385.69  3995.3 1384.12  4038.3 1384.55  4101.8 1382.00  4260.4 1371.98
  4440.2 1369.56  4489.9 1366.08  4495.1 1366.36  4503.6 1369.39  4521.1 1369.83
  4757.4 1371.52  4864.7 1370.60  4927.2 1372.68  4937.2 1371.76  4953.2 1365.93
  4984.4 1362.83  4990.1 1360.46  5004.9 1360.26  5005.4 1359.76  5024.0 1360.26
  5057.0 1360.49  5118.8 1365.52  5198.8 1373.61  5219.7 1373.39  5241.3 1376.19
  5248.1 1375.66  5276.4 1380.52  5298.0 1382.21  5340.5 1390.27  5354.4 1390.99
#Mann=4,-1,0
  3953.8    0.05       0  5004.9    0.05       0  5024.0    0.05       0
  5118.8    0.12       0
Bank Sta=5004.9,5024
Exp/Cntr=0.3,0.1

Type RM Length L Ch R = 1,500,0,0,0
BEGIN DESCRIPTION:
LEFT HAND CREEK 1.0
END DESCRIPTION:
XS GIS Cut Line= 3
      2738930.66     10173178.08      2739142.07     10173426.89
      2739555.67     10173803.10
#Sta/Elev= 30
  4673.5 1370.31  4808.6 1368.99  4822.9 1367.65  4837.2 1362.39  4843.8 1358.78
  4858.1 1361.80  4872.3 1361.89  4893.2 1365.12  4900.9 1363.91  4921.8 1364.45
  4956.9 1362.34  4978.9 1359.01  4983.6 1356.49  4984.1 1355.99  5002.7 1356.49
  5028.3 1356.94  5035.1 1358.78  5049.3 1365.48  5056.7 1367.90  5070.9 1368.58
  5099.3 1369.45  5148.6 1368.86  5169.6 1365.24  5219.6 1363.89  5240.5 1366.51
  5283.1 1369.65  5311.5 1369.39  5481.1 1377.84  5516.9 1377.44  5559.1 1378.65
#Mann=3,-1,0
  4673.5    0.05       0  4983.6    0.05       0  5002.7    0.05       0
Bank Sta=4983.6,5002.7
Exp/Cntr=0.3,0.1

Chan Stop Cuts=-1