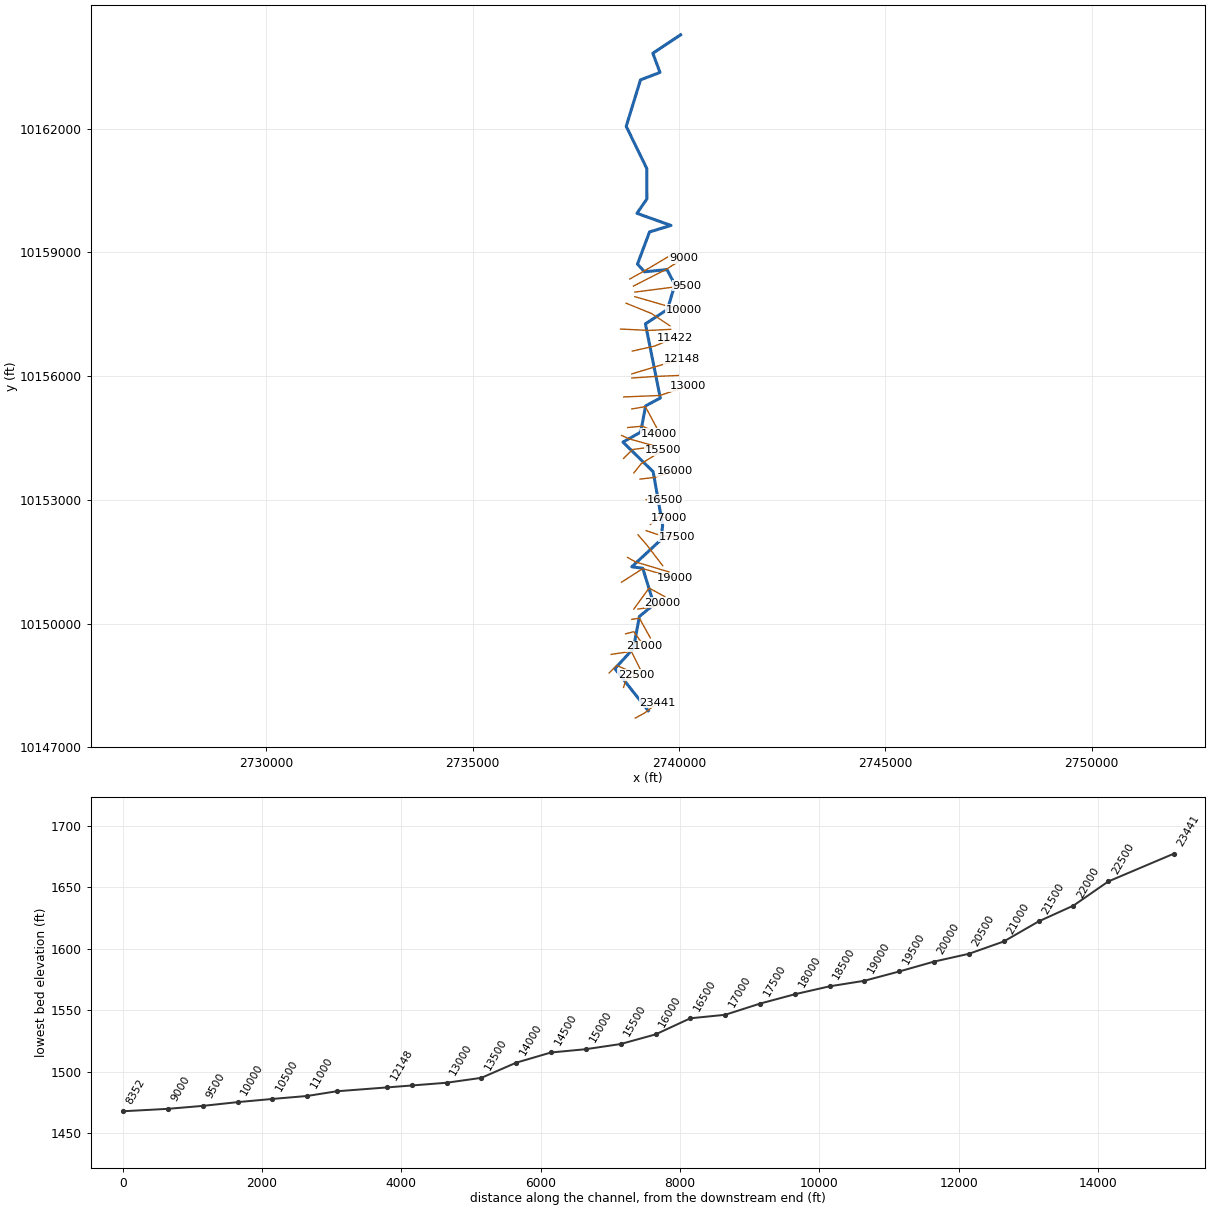
--- LITTLE COTTONWOOD CREEK.prj (project) ---

Proj Title=LITTLE COTTONWOOD CREEK Base Level Engineering
Current Plan=p01
Default Exp/Contr=0.3,0.1
English Units
Geom File=g01
Flow File=f01
Plan File=p01
Y Axis Title=Elevation
X Axis Title(PF)=Main Channel Distance
X Axis Title(XS)=Station
BEGIN DESCRIPTION:
LITTLE COTTONWOOD CREEK
END DESCRIPTION:
DSS Export Rating Curves= 0
DSS Export Rating Curve Sorted= 0
DSS Export Volume Flow Curves= 0
DXF OffsetX= 0
DXF OffsetY= 0
DXF ScaleX= 1
DXF ScaleY= 10

--- LITTLE COTTONWOOD CREEK.p01 (plan) ---

Plan Title=Multiple Run
Short Identifier=Multiple
Geom File=g01
Flow File=f01
Subcritical Flow
K Sum by GR= 0
Std Step Tol= 0.01
Critical Tol= 0.01
Num of Std Step Trials= 20
Max Error Tol= 0.3
Flow Tol Ratio= 0.001
Split Flow NTrial= 30
Split Flow Tol= 0.02
Split Flow Ratio= 0.02
Log Output Level= 0
Friction Slope Method= 1
Unsteady Friction Slope Method= 2
Unsteady Bridges Friction Slope Method= 1
Parabolic Critical Depth
Global Vel Dist=  1 , 1 , 1
Global Log Level= 0
CheckData=True
Encroach Param= -1, 0, 0, 0
BEGIN DESCRIPTION:
Multiple Run
END DESCRIPTION:

--- LITTLE COTTONWOOD CREEK.f01 (steady flow) ---

Flow Title=Multiple
Program Version=4.10
Number of Profiles= 7
Profile Names=10-year,25-year,50-year,1pct_min,100-year,1pct_plu,500-year
River Rch & RM=LITTLE COTTONWOO,Reach-1         ,23441
     521     855    1763    1373    2496    4536    3634
River Rch & RM=LITTLE COTTONWOO,Reach-1         ,18500
     739    1245    2518    1862    3601    6963    5235
River Rch & RM=LITTLE COTTONWOO,Reach-1         ,13000
    1085    1879    3608    2550    5190   10562    7477
River Rch & RM=LITTLE COTTONWOO,Reach-1         ,5000
    1148    1999    3764    2626    5416   11169    7793
River Rch & RM=LITTLE COTTONWOO,Reach-1         ,2989
    1487    2624    5149    3613    7479   15484   10722
Boundary for River Rch & Prof#=LITTLE COTTONWOO,Reach-1         , 1
Up Type= 0
Dn Type= 3
Dn Slope=0.005
Boundary for River Rch & Prof#=LITTLE COTTONWOO,Reach-1         , 2
Up Type= 0
Dn Type= 3
Dn Slope=0.005
Boundary for River Rch & Prof#=LITTLE COTTONWOO,Reach-1         , 3
Up Type= 0
Dn Type= 3
Dn Slope=0.005
Boundary for River Rch & Prof#=LITTLE COTTONWOO,Reach-1         , 4
Up Type= 0
Dn Type= 3
Dn Slope=0.005
Boundary for River Rch & Prof#=LITTLE COTTONWOO,Reach-1         , 5
Up Type= 0
Dn Type= 3
Dn Slope=0.005
Boundary for River Rch & Prof#=LITTLE COTTONWOO,Reach-1         , 6
Up Type= 0
Dn Type= 3
Dn Slope=0.005
Boundary for River Rch & Prof#=LITTLE COTTONWOO,Reach-1         , 7
Up Type= 0
Dn Type= 3
Dn Slope=0.005
DSS Import GetInterval= 0
DSS Import GetPeak= 0
DSS Import FillOption= 0

--- LITTLE COTTONWOOD CREEK.g01 (geometry) ---

Geom Title=Existing Conditions
Program Version=4.10

River Reach=LITTLE COTTONWOO,Reach-1
Reach XY= 30
      2739254.25       10147888.       2738445.5       10148908.
      2738895.25       10149398.        2739041.       10150175.
       2739393.5       10150464.        2739121.       10151342.
      2738855.25       10151377.      2739560.25       10152030.
        2739604.       10152380.      2739373.75       10153682.
      2738641.75       10154400.      2739071.75       10154642.
       2739191.5       10155279.      2739546.75       10155468.
      2739186.25       10157266.       2739719.5       10157615.
      2739900.75       10158217.      2739709.25       10158582.
      2739164.25       10158528.      2738994.25       10158715.
       2739286.5       10159495.        2739806.       10159652.
      2738980.75       10159945.       2739221.5       10160295.
       2739218.5       10161033.       2738720.5       10162055.
      2739066.25       10163180.      2739539.25       10163361.
        2739365.       10163825.        2740039.       10164273.

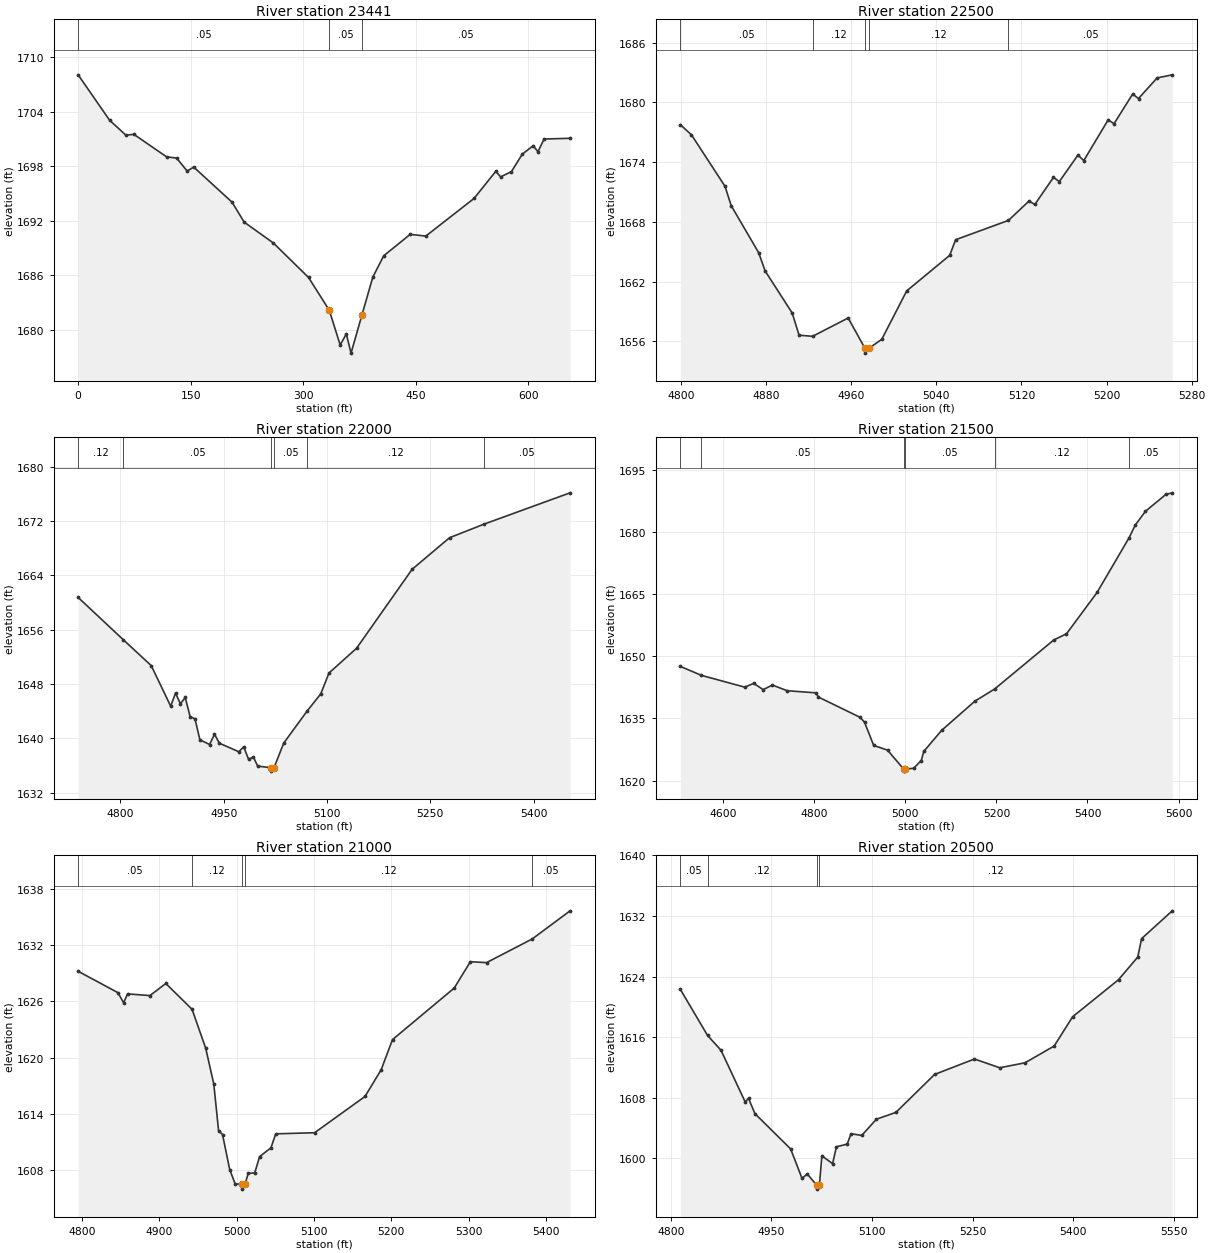
Type RM Length L Ch R = 1 ,23441   ,941,941,941
BEGIN DESCRIPTION:
LITTLE COTTONWOOD CREEK 46.0
END DESCRIPTION:
XS GIS Cut Line= 3
      2738940.61     10147709.79      2739166.41     10147833.34
      2739481.69     10148077.26
#Sta/Elev= 30
       0 1708.08    41.9 1703.08    63.7 1701.43    74.2 1701.53   117.8 1699.05
   131.2 1698.91   145.3 1697.48     154 1697.92   205.1 1694.05   221.2 1691.86
   260.1 1689.56     307 1685.76   334.6 1682.15   349.1 1678.33   357.3 1679.54
   363.6 1677.43   378.1 1681.63   392.6  1685.8   407.1 1688.15   442.4 1690.51
   463.2 1690.32   527.5 1694.47   556.5 1697.46   562.8 1696.84   577.3 1697.42
   591.8 1699.35   606.3 1700.27   612.6 1699.61   620.8 1701.01   655.4 1701.09
#Mann= 3 , 0 , 0
       0     .05       0   334.6     .05       0   378.1     .05       0
Bank Sta=334.6,378.1
XS Rating Curve= 0 ,0
Exp/Cntr=0.3,0.1

Type RM Length L Ch R = 1 ,22500   ,500,500,500
BEGIN DESCRIPTION:
LITTLE COTTONWOOD CREEK 45.0
END DESCRIPTION:
XS GIS Cut Line= 3
       2738655.7     10148453.16      2738717.91     10148643.76
      2738955.67     10148753.11
#Sta/Elev= 30
  4799.5 1677.77    4810 1676.74  4841.5 1671.57  4847.3 1669.63  4873.1 1664.91
  4879.2 1663.07  4904.6 1658.85  4911.1 1656.62  4923.8 1656.51  4957.2 1658.35
  4972.9 1655.32  4973.1 1654.82  4976.9 1655.32  4988.8 1656.21  5012.2 1661.07
  5052.6 1664.64  5058.2 1666.21  5107.8 1668.15  5127.1 1670.09  5132.6 1669.75
  5150.1 1672.47  5155.6 1672.05  5173.1 1674.71  5178.6 1674.16  5201.5 1678.25
    5207 1677.86  5224.5 1680.84    5230 1680.39  5247.5 1682.46  5261.7 1682.77
#Mann= 5 ,-1 , 0
  4799.5     .05       0  4923.8     .12       0  4972.9     .07       0
  4976.9     .12       0  5107.8     .05       0
Bank Sta=4972.9,4976.9
XS Rating Curve= 0 ,0
Exp/Cntr=0.3,0.1

Type RM Length L Ch R = 1 ,22000   ,500,500,500
BEGIN DESCRIPTION:
LITTLE COTTONWOOD CREEK 44.0
END DESCRIPTION:
XS GIS Cut Line= 3
      2738305.68     10148803.11      2738491.57     10148986.76
      2738905.67     10148803.12
#Sta/Elev= 30
  4738.7 1660.74  4804.5 1654.49  4844.8 1650.71  4873.1 1644.73  4880.1 1646.66
  4887.2 1645.08  4894.2 1646.01  4901.3  1643.2  4908.4 1642.86  4915.5 1639.78
  4929.6 1639.09  4936.7  1640.6  4943.8 1639.28  4972.1 1638.02  4979.1 1638.75
  4986.2 1636.91  4993.2 1637.25  4999.4 1635.91  5019.1 1635.67  5019.4 1635.17
  5023.1 1635.67  5037.3 1639.31  5071.3 1644.03  5090.9 1646.53    5103 1649.62
    5143 1653.26  5223.7 1664.89    5278 1669.53  5327.8 1671.52    5453 1676.14
#Mann= 6 ,-1 , 0
  4738.7     .12       0  4804.5     .05       0  5019.1     .05       0
  5023.1     .05       0  5071.3     .12       0  5327.8     .05       0
Bank Sta=5019.1,5023.1
XS Rating Curve= 0 ,0
Exp/Cntr=0.3,0.1

Type RM Length L Ch R = 1 ,21500   ,500,500,500
BEGIN DESCRIPTION:
LITTLE COTTONWOOD CREEK 43.0
END DESCRIPTION:
XS GIS Cut Line= 3
      2738355.69     10149253.11      2738844.41     10149327.87
      2739105.68     10148803.12
#Sta/Elev= 30
  4505.6 1647.55  4551.8 1645.39  4647.2 1642.54  4666.7 1643.46  4687.7 1641.94
  4707.9 1643.05  4740.2 1641.68  4803.6 1641.17  4809.1 1640.15  4900.1 1635.29
  4910.2 1634.11  4930.4 1628.49  4960.8 1627.36  4996.1  1622.8  4996.4  1622.3
  5000.1  1622.8  5018.1 1622.99  5034.9 1624.86  5040.5 1627.06  5079.7 1632.13
  5152.4 1639.14  5196.2 1642.11  5325.9 1653.91  5353.9  1655.4  5421.1 1665.37
  5491.4 1678.55  5505.1 1681.63  5527.4 1684.93  5572.2    1689  5586.2 1689.38
#Mann= 6 ,-1 , 0
  4505.6     .12       0  4551.8     .05       0  4996.1     .05       0
  5000.1     .05       0  5196.2     .12       0  5491.4     .05       0
Bank Sta=4996.1,5000.1
XS Rating Curve= 0 ,0
Exp/Cntr=0.3,0.1

Type RM Length L Ch R = 1 ,21000   ,500,500,500
BEGIN DESCRIPTION:
LITTLE COTTONWOOD CREEK 42.0
END DESCRIPTION:
XS GIS Cut Line= 3
      2738705.73     10149753.12      2738904.22     10149803.57
      2739155.66     10149453.14
#Sta/Elev= 30
  4795.2 1629.19  4846.7 1626.91    4854 1625.83  4859.1 1626.78    4888  1626.6
  4908.6 1627.89  4942.5 1625.14  4960.2 1620.98  4970.6 1617.18  4976.8 1612.21
  4981.9  1611.8  4991.2 1608.06  4998.2 1606.55  5006.9 1606.48  5007.1 1605.98
  5010.9 1606.48  5015.1 1607.66  5023.6 1607.71  5029.8 1609.44  5044.5 1610.38
  5050.7 1611.87    5101 1611.99  5166.1 1615.85    5187 1618.69  5201.7 1621.91
  5281.5  1627.4  5302.4 1630.21  5323.3 1630.11  5382.5 1632.64  5431.3 1635.63
#Mann= 5 ,-1 , 0
  4795.2     .05       0  4942.5     .12       0  5006.9     .07       0
  5010.9     .12       0  5382.5     .05       0
Bank Sta=5006.9,5010.9
XS Rating Curve= 0 ,0
Exp/Cntr=0.3,0.1

Type RM Length L Ch R = 1 ,20500   ,500,500,500
BEGIN DESCRIPTION:
LITTLE COTTONWOOD CREEK 41.0
END DESCRIPTION:
XS GIS Cut Line= 3
      2738855.68     10150103.11      2739039.25     10150131.78
      2739305.67     10149653.13
#Sta/Elev= 30
  4814.2 1622.32  4854.8 1616.23  4874.9 1614.27  4910.9 1607.45  4915.9 1607.92
  4925.5  1605.9  4978.7 1601.25  4995.7 1597.36  5003.6 1597.94  5017.6 1596.44
  5017.8 1595.94  5021.6 1596.44  5025.3 1600.33  5041.3 1599.31    5047 1601.53
    5063 1601.88  5068.8 1603.25  5084.8 1603.03  5106.5 1605.16  5135.8 1606.08
  5193.4 1611.08  5252.8 1613.12  5290.6 1611.96  5328.3 1612.62  5371.7 1614.83
  5399.2 1618.69  5467.7 1623.59  5496.4 1626.58  5502.1 1629.01  5547.8 1632.68
#Mann= 4 ,-1 , 0
  4814.2     .05       0  4854.8     .12       0  5017.6     .07       0
  5021.6     .12       0
Bank Sta=5017.6,5021.6
XS Rating Curve= 0 ,0
Exp/Cntr=0.3,0.1

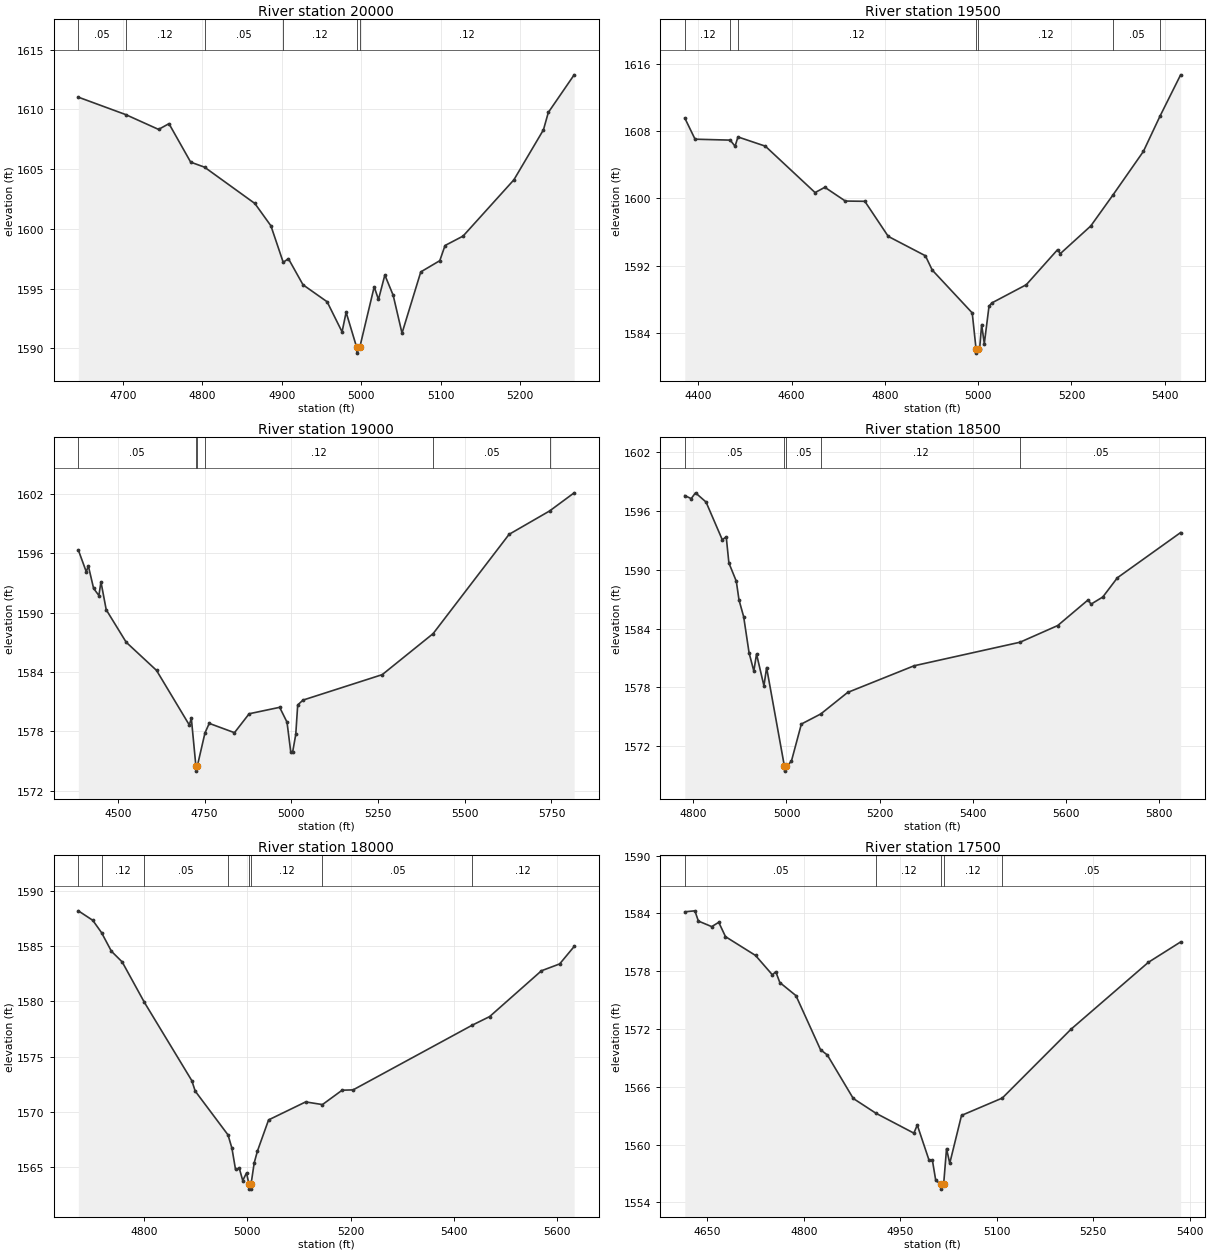
Type RM Length L Ch R = 1 ,20000   ,500,500,500
BEGIN DESCRIPTION:
LITTLE COTTONWOOD CREEK 40.0
END DESCRIPTION:
XS GIS Cut Line= 3
      2739005.65     10150353.11      2739358.34     10150400.85
      2739605.73     10150503.13
#Sta/Elev= 30
  4644.1 1611.03  4703.7 1609.57    4745 1608.33  4758.1 1608.81  4785.4 1605.59
  4802.8 1605.17  4866.1 1602.13  4886.3 1600.26  4901.8  1597.2  4908.3 1597.51
  4926.7 1595.32    4957  1593.9  4975.8 1591.38  4980.9 1593.02  4994.1  1590.1
  4994.4  1589.6  4998.1  1590.1  5016.2 1595.15  5021.6 1594.09  5029.6 1596.14
  5040.1 1594.44  5051.2 1591.27  5074.8  1596.4  5098.7 1597.34  5105.3 1598.61
    5128  1599.4  5191.9 1604.11  5229.1  1608.3  5235.2 1609.75  5267.7  1612.9
#Mann= 6 ,-1 , 0
  4644.1     .05       0  4703.7     .12       0  4802.8     .05       0
  4901.8     .12       0  4994.1     .07       0  4998.1     .12       0
Bank Sta=4994.1,4998.1
XS Rating Curve= 0 ,0
Exp/Cntr=0.3,0.1

Type RM Length L Ch R = 1 ,19500   ,500,500,500
BEGIN DESCRIPTION:
LITTLE COTTONWOOD CREEK 39.0
END DESCRIPTION:
XS GIS Cut Line= 3
      2738905.71     10150353.15      2739275.35     10150862.33
       2739655.7      10150653.1
#Sta/Elev= 30
  4370.8 1609.57  4392.8 1607.05  4468.2 1606.94  4478.6 1606.21  4484.8 1607.32
  4543.5 1606.22  4650.2 1600.69  4671.1 1601.32  4715.1 1599.68  4756.9 1599.65
  4807.1 1595.47  4886.8 1593.16  4901.4 1591.46  4987.2 1586.35  4995.4 1582.06
  4995.6 1581.56  4999.4 1582.06    5003 1582.06  5007.4 1584.96  5013.1 1582.69
  5023.2 1587.15  5029.2 1587.54  5103.1 1589.71  5170.3 1593.89    5176 1593.41
  5241.4 1596.71  5289.2 1600.42  5354.2 1605.59  5389.9  1609.8  5434.1 1614.72
#Mann= 7 ,-1 , 0
  4370.8     .12       0  4468.2     .05       0  4484.8     .12       0
  4995.4     .07       0  4999.4     .12       0  5289.2     .05       0
  5389.9     .12       0
Bank Sta=4995.4,4999.4
XS Rating Curve= 0 ,0
Exp/Cntr=0.3,0.1

Type RM Length L Ch R = 1 ,19000   ,500,500,500
BEGIN DESCRIPTION:
LITTLE COTTONWOOD CREEK 38.0
END DESCRIPTION:
XS GIS Cut Line= 3
      2738605.65     10151003.09      2739123.36      10151333.4
      2739905.67     10151103.12
#Sta/Elev= 30
  4385.9 1596.31  4408.8 1594.11  4414.7 1594.71  4429.9 1592.44  4445.2 1591.71
  4451.1  1593.1  4466.3 1590.28  4523.9    1587  4611.3 1584.16  4705.8 1578.65
  4711.7 1579.33  4724.9 1574.49  4725.2 1573.99  4728.9 1574.49    4751 1577.84
  4763.3 1578.81  4836.1 1577.87  4878.4 1579.78  4966.4 1580.43  4987.6 1578.93
  4998.4 1575.92  5003.8 1575.92  5012.8 1577.69  5018.4 1580.67  5033.7 1581.16
  5262.2 1583.73  5408.9 1587.87  5627.9 1597.89  5744.7 1600.25  5815.5 1602.08
#Mann= 6 ,-1 , 0
  4385.9     .05       0  4724.9     .07       0  4728.9     .05       0
    4751     .12       0  5408.9     .05       0  5744.7     .12       0
Bank Sta=4724.9,4728.9
XS Rating Curve= 0 ,0
Exp/Cntr=0.3,0.1

Type RM Length L Ch R = 1 ,18500   ,500,500,500
BEGIN DESCRIPTION:
LITTLE COTTONWOOD CREEK 37.0
END DESCRIPTION:
XS GIS Cut Line= 3
      2738755.65     10151603.13      2738945.61     10151495.97
      2739755.69     10151253.11
#Sta/Elev= 30
  4781.9 1597.56  4795.6 1597.25  4804.9 1597.84  4827.5  1596.9  4862.3 1593.06
  4870.8 1593.35  4876.5 1590.69  4892.4 1588.83  4898.2 1586.92  4908.2 1585.21
  4919.8 1581.53    4930 1579.67  4935.8 1581.41  4951.7 1578.16  4957.4 1580.03
  4995.6 1569.97  4995.9 1569.47    5000 1569.97  5010.5 1570.46    5032 1574.27
  5073.7  1575.3  5131.2 1577.49  5273.9 1580.21  5501.1 1582.61    5582 1584.31
  5647.3 1586.93  5653.4 1586.49  5678.7 1587.22    5710 1589.18  5845.7 1593.79
#Mann= 5 ,-1 , 0
  4781.9     .05       0  4995.6     .05       0    5000     .05       0
  5073.7     .12       0  5501.1     .05       0
Bank Sta=4995.6,5000
XS Rating Curve= 0 ,0
Exp/Cntr=0.3,0.1

Type RM Length L Ch R = 1 ,18000   ,500,500,500
BEGIN DESCRIPTION:
LITTLE COTTONWOOD CREEK 36.0
END DESCRIPTION:
XS GIS Cut Line= 3
      2739005.67     10152153.12       2739220.4     10151905.71
      2739605.69      10151403.1
#Sta/Elev= 30
  4672.4 1588.21  4700.4 1587.35  4717.3 1586.24  4736.5 1584.55  4757.4 1583.58
  4800.4 1579.92  4892.3 1572.83  4898.9 1571.88  4962.5 1567.91  4970.1  1566.7
    4977 1564.79  4984.4 1564.88    4991 1563.78  4998.4 1564.47  5002.8  1563.5
  5003.1    1563  5006.9    1563  5007.3  1563.5  5013.2 1565.37  5019.5 1566.45
  5041.1 1569.27  5112.9  1570.9  5145.5 1570.66  5183.6 1571.96  5204.9 1571.99
  5435.7 1577.85  5469.5 1578.63  5569.9 1582.78  5605.2  1583.4  5633.3 1584.98
#Mann= 8 ,-1 , 0
  4672.4     .05       0  4717.3     .12       0  4800.4     .05       0
  4962.5     .12       0  5002.8     .07       0  5007.3     .12       0
  5145.5     .05       0  5435.7     .12       0
Bank Sta=5002.8,5007.3
XS Rating Curve= 0 ,0
Exp/Cntr=0.3,0.1

Type RM Length L Ch R = 1 ,17500   ,500,500,500
BEGIN DESCRIPTION:
LITTLE COTTONWOOD CREEK 35.0
END DESCRIPTION:
XS GIS Cut Line= 3
      2739205.69     10152253.11       2739570.5     10152129.75
      2739955.68     10152103.11
#Sta/Elev= 30
  4614.9 1584.16  4630.6 1584.26    4636  1583.2  4656.8 1582.62  4667.7 1583.07
  4678.2 1581.58  4724.9 1579.63  4751.1 1577.62  4756.4 1577.94  4762.7 1576.82
  4787.8 1575.46    4826 1569.85  4836.6  1569.3  4876.9 1564.79  4912.3 1563.25
  4971.2 1561.19  4976.5 1562.03  4994.8 1558.38    5000 1558.38  5005.2 1556.29
    5013 1555.88  5013.3 1555.38  5017.5 1555.88    5022 1559.58    5027 1558.06
  5045.3 1563.03  5108.7 1564.83  5215.7 1571.98    5336 1578.92  5386.1 1581.03
#Mann= 5 ,-1 , 0
  4614.9     .05       0  4912.3     .12       0    5013     .07       0
  5017.5     .12       0  5108.7     .05       0
Bank Sta=5013,5017.5
XS Rating Curve= 0 ,0
Exp/Cntr=0.3,0.1

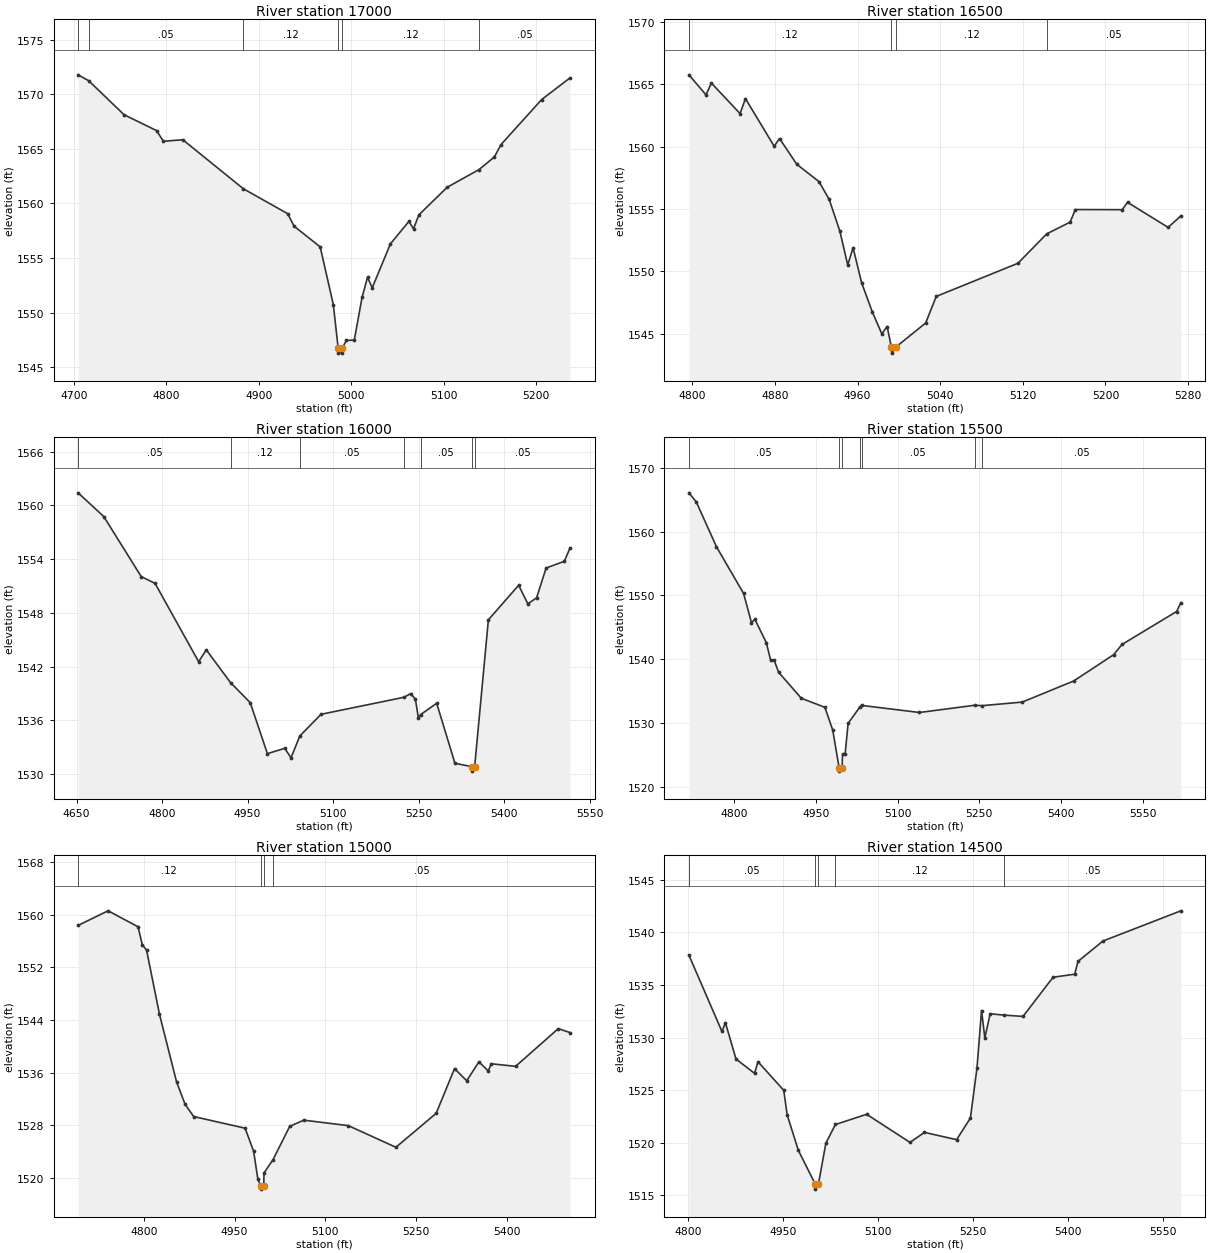
Type RM Length L Ch R = 1 ,17000   ,500,500,500
BEGIN DESCRIPTION:
LITTLE COTTONWOOD CREEK 34.0
END DESCRIPTION:
XS GIS Cut Line= 3
      2739305.68     10152403.11      2739524.19      10152601.9
       2739755.7     10152553.11
#Sta/Elev= 30
  4704.6 1571.79    4716 1571.25  4754.3 1568.13  4789.4 1566.68  4796.8  1565.7
  4817.8 1565.84  4883.4 1561.34  4931.3 1559.06  4938.1 1557.92  4966.4 1556.02
  4980.6 1550.73  4985.8 1546.78  4986.1 1546.28    4990 1546.28  4990.4 1546.78
  4994.8 1547.44  5003.3 1547.48  5011.7 1551.39  5017.6 1553.23  5022.7 1552.27
  5042.4  1556.3  5062.3 1558.35  5067.4 1557.68  5073.1 1558.95  5103.7 1561.48
  5138.1  1563.1  5154.8 1564.26  5161.9 1565.39  5205.9 1569.52  5236.6 1571.51
#Mann= 6 ,-1 , 0
  4704.6     .12       0    4716     .05       0  4883.4     .12       0
  4985.8     .07       0  4990.4     .12       0  5138.1     .05       0
Bank Sta=4985.8,4990.4
XS Rating Curve= 0 ,0
Exp/Cntr=0.3,0.1

Type RM Length L Ch R = 1 ,16500   ,500,500,500
BEGIN DESCRIPTION:
LITTLE COTTONWOOD CREEK 33.0
END DESCRIPTION:
XS GIS Cut Line= 3
      2739205.69     10153003.11      2739400.25     10153061.72
      2739667.73     10153007.08
#Sta/Elev= 30
  4796.8 1565.76  4813.3 1564.15  4818.5  1565.1  4846.3 1562.65  4851.5 1563.85
  4879.3 1560.03  4884.5 1560.65  4901.2 1558.58  4922.7 1557.19  4932.6 1555.76
    4943 1553.19  4950.5  1550.5  4955.7 1551.89  4963.9 1549.09  4974.3 1546.74
  4983.5 1544.98  4988.7 1545.56  4992.7 1543.93  4993.1 1543.43  4997.3 1543.93
    5026 1545.85  5036.2 1547.98  5115.3 1550.64  5143.2    1553  5165.8 1553.94
  5170.9 1554.95  5216.3 1554.94  5221.4 1555.53  5260.7 1553.52    5273 1554.44
#Mann= 4 ,-1 , 0
  4796.8     .12       0  4992.7     .07       0  4997.3     .12       0
  5143.2     .05       0
Bank Sta=4992.7,4997.3
XS Rating Curve= 0 ,0
Exp/Cntr=0.3,0.1

Type RM Length L Ch R = 1 ,16000   ,500,500,500
BEGIN DESCRIPTION:
LITTLE COTTONWOOD CREEK 32.0
END DESCRIPTION:
XS GIS Cut Line= 3
      2739055.64     10153503.11      2739400.75     10153541.99
      2739891.42     10153700.72
#Sta/Elev= 30
  4652.7 1561.41  4697.7 1558.76  4763.4 1552.05  4787.7 1551.29  4864.1 1542.54
  4877.6 1543.86  4920.1  1540.2  4954.6 1537.97  4984.8 1532.26  5015.2 1532.86
  5026.2 1531.79  5041.6 1534.23  5078.8 1536.66  5224.2 1538.56  5236.4 1538.98
  5244.5 1538.33  5249.7 1536.25  5253.6 1536.63  5281.8 1537.89  5313.8 1531.19
  5343.2 1530.81  5343.6 1530.31  5348.4 1530.81  5372.5 1547.22  5425.6 1551.08
  5441.8    1549  5457.1 1549.68  5473.8 1553.01  5505.8 1553.76  5515.7 1555.25
#Mann= 7 ,-1 , 0
  4652.7     .05       0  4920.1     .12       0  5041.6     .05       0
  5224.2     .12       0  5253.6     .05       0  5343.2     .07       0
  5348.4     .05       0
Bank Sta=5343.2,5348.4
XS Rating Curve= 0 ,0
Exp/Cntr=0.3,0.1

Type RM Length L Ch R = 1 ,15500   ,500,500,500
BEGIN DESCRIPTION:
LITTLE COTTONWOOD CREEK 31.0
END DESCRIPTION:
XS GIS Cut Line= 3
      2738905.69     10153653.12      2739081.44     10153873.79
      2739605.68     10154203.11
#Sta/Elev= 30
  4717.9 1566.06  4731.5 1564.61  4768.3 1557.62    4818  1550.3  4832.4 1545.75
  4838.8 1546.24  4859.6 1542.61  4867.6 1539.83    4874 1539.84  4882.1 1537.98
  4923.7  1533.9  4966.9 1532.48  4981.3 1528.92  4993.1 1522.99  4993.6 1522.49
  4998.4 1522.99  4999.4  1525.2  5004.1  1525.2  5009.5 1529.97  5031.7  1532.6
  5034.1 1532.78  5140.3 1531.67  5241.2  1532.8  5255.1 1532.74  5328.7  1533.3
    5423 1536.61    5496 1540.72  5511.3 1542.32  5611.4 1547.48  5619.1 1548.85
#Mann= 7 ,-1 , 0
  4717.9     .05       0  4993.1     .05       0  4998.4     .05       0
  5031.7     .12       0  5034.1     .05       0  5241.2     .12       0
  5255.1     .05       0
Bank Sta=4993.1,4998.4
XS Rating Curve= 0 ,0
Exp/Cntr=0.3,0.1

Type RM Length L Ch R = 1 ,15000   ,500,500,500
BEGIN DESCRIPTION:
LITTLE COTTONWOOD CREEK 30.0
END DESCRIPTION:
XS GIS Cut Line= 3
       2738655.7     10154003.13      2738874.95     10154220.03
      2739374.85     10154285.68
#Sta/Elev= 30
  4691.6 1558.36  4741.1 1560.57  4790.5 1558.15  4797.6 1555.43  4804.7 1554.59
  4825.9 1544.88  4854.2 1534.58  4868.4 1531.15  4882.5 1529.31  4967.4 1527.54
  4981.5 1524.05  4988.5 1519.81    4993 1518.78  4993.4 1518.28  4998.3 1518.78
  4998.6 1520.73  5013.7 1522.78  5041.1 1527.81  5064.2 1528.76  5137.9 1527.93
  5216.6 1524.64  5283.1  1529.8  5313.4 1536.59  5333.6 1534.75  5353.7 1537.62
  5369.1 1536.24  5374.1 1537.33  5414.3 1536.94  5484.9 1542.67  5504.2 1542.07
#Mann= 4 ,-1 , 0
  4691.6     .12       0    4993     .07       0  4998.3     .12       0
  5013.7     .05       0
Bank Sta=4993,4998.3
XS Rating Curve= 0 ,0
Exp/Cntr=0.3,0.1

Type RM Length L Ch R = 1 ,14500   ,500,500,500
BEGIN DESCRIPTION:
LITTLE COTTONWOOD CREEK 29.0
END DESCRIPTION:
XS GIS Cut Line= 3
       2738608.1     10154562.01      2738788.77     10154479.31
      2739345.89     10154324.23
#Sta/Elev= 30
  4801.3 1537.82  4853.4 1530.58  4858.9 1531.41  4875.6 1527.96  4904.9  1526.6
  4910.4  1527.7    4951 1524.99  4956.5 1522.65    4974  1519.3  5000.6  1516.1
    5001  1515.6  5005.9  1516.1  5017.6 1519.97  5032.7 1521.74    5082 1522.71
  5150.5 1520.04  5173.3 1520.99  5224.1  1520.3  5245.9 1522.35  5256.3 1527.11
  5263.5 1532.57  5268.7 1529.96  5277.1 1532.26    5299 1532.13    5329 1532.01
  5376.5 1535.73  5410.7 1536.02  5415.9 1537.24  5455.3 1539.17  5578.3 1542.04
#Mann= 5 ,-1 , 0
  4801.3     .05       0  5000.6     .05       0  5005.9     .05       0
  5032.7     .12       0    5299     .05       0
Bank Sta=5000.6,5005.9
XS Rating Curve= 0 ,0
Exp/Cntr=0.3,0.1

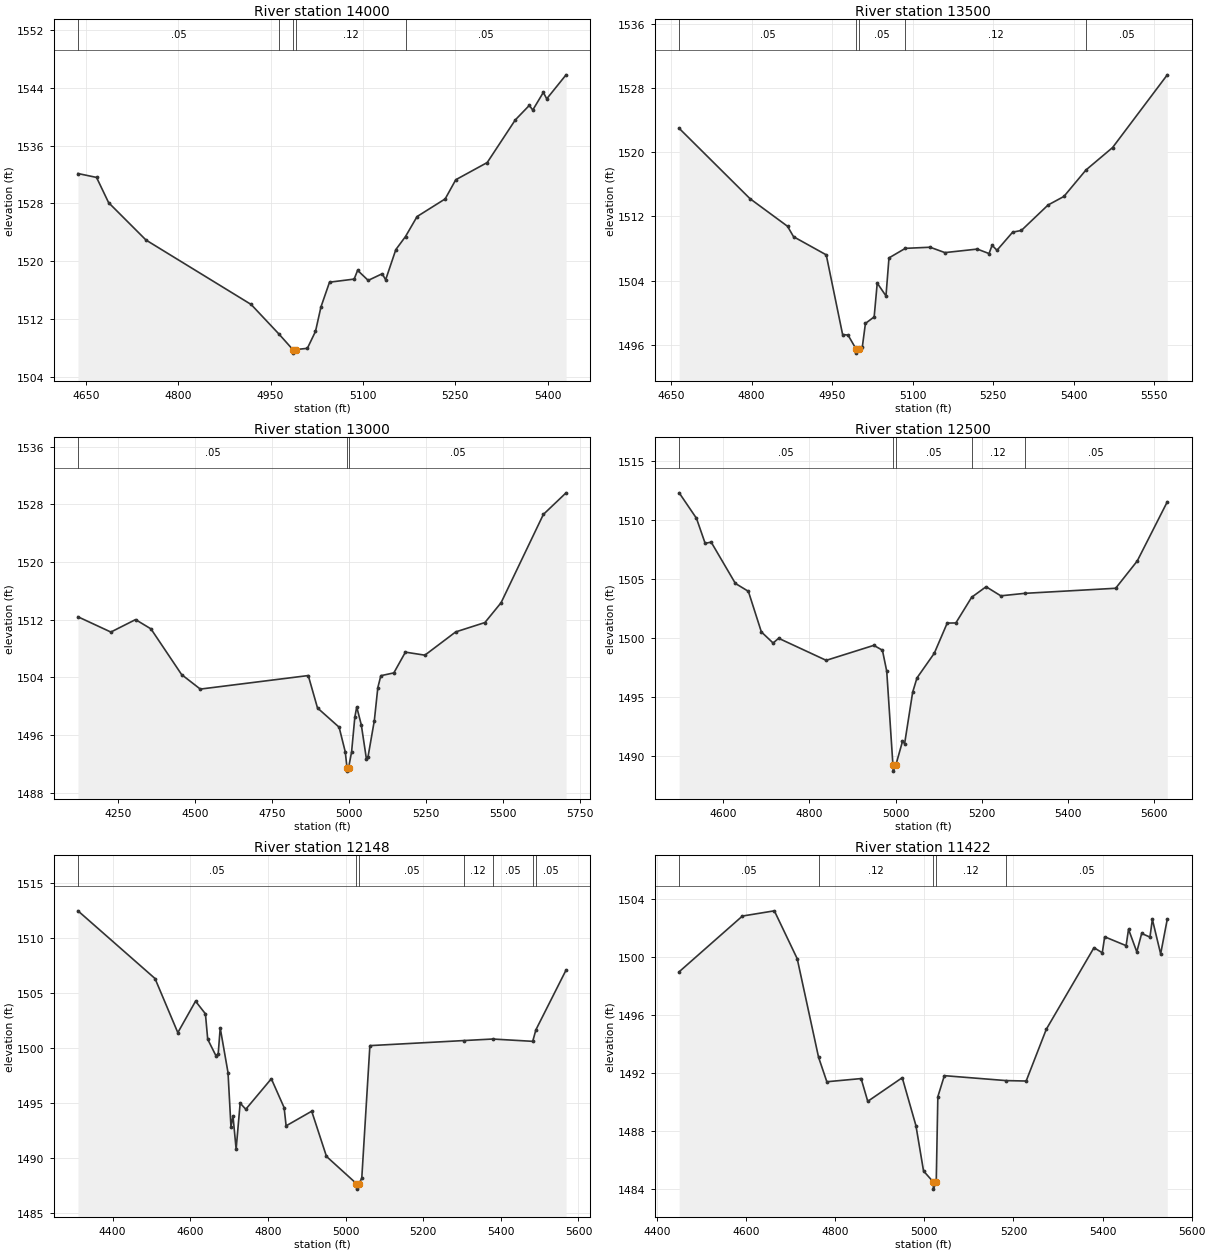
Type RM Length L Ch R = 1 ,14000   ,500,500,500
BEGIN DESCRIPTION:
LITTLE COTTONWOOD CREEK 28.0
END DESCRIPTION:
XS GIS Cut Line= 3
      2738755.66     10154753.11      2739116.82      10154786.5
      2739505.65     10154603.13
#Sta/Elev= 30
  4637.3 1532.14  4667.5  1531.6  4687.1 1528.11  4747.8 1522.94  4918.5 1514.03
  4963.8 1509.93  4986.1  1507.8  4986.5  1507.3  4991.5  1507.8  5009.8 1507.96
    5023  1510.3  5031.9 1513.69  5045.8 1517.11  5085.8 1517.54  5091.4 1518.75
  5108.6 1517.36  5131.4 1518.28  5136.9 1517.44  5153.5 1521.62  5169.2 1523.43
    5188 1526.19  5233.6 1528.63  5250.8 1531.28  5301.9 1533.66  5347.4 1539.55
  5370.2 1541.56  5375.8 1540.92    5393 1543.36  5398.5 1542.47  5429.9 1545.79
#Mann= 5 ,-1 , 0
  4637.3     .05       0  4963.8     .12       0  4986.1     .07       0
  4991.5     .12       0  5169.2     .05       0
Bank Sta=4986.1,4991.5
XS Rating Curve= 0 ,0
Exp/Cntr=0.3,0.1

Type RM Length L Ch R = 1 ,13500   ,500,500,500
BEGIN DESCRIPTION:
LITTLE COTTONWOOD CREEK 27.0
END DESCRIPTION:
XS GIS Cut Line= 3
      2738855.65     10155203.11      2739185.77     10155260.09
      2739455.71     10154753.07
#Sta/Elev= 30
    4665 1522.98    4797 1514.21  4866.9 1510.77  4878.1 1509.47    4939 1507.21
  4969.5 1497.28  4979.6 1497.21  4994.7 1495.46  4995.1 1494.96  5000.1 1495.46
  5006.3 1495.77    5012 1498.66  5028.3 1499.48    5034 1503.69  5050.3 1502.09
  5055.9 1506.83  5086.3 1508.02  5132.5 1508.16  5160.1 1507.49  5220.4 1507.93
  5242.3 1507.37    5248  1508.4  5257.1 1507.78  5286.3 1510.04  5302.5 1510.25
  5352.2 1513.42  5381.8 1514.49  5422.9 1517.79  5472.4 1520.58  5574.4 1529.65
#Mann= 5 ,-1 , 0
    4665     .05       0  4994.7     .03       0  5000.1     .05       0
  5086.3     .12       0  5422.9     .05       0
Bank Sta=4994.7,5000.1
XS Rating Curve= 0 ,0
Exp/Cntr=0.3,0.1

Type RM Length L Ch R = 1 ,13000   ,500,500,500
BEGIN DESCRIPTION:
LITTLE COTTONWOOD CREEK 26.0
END DESCRIPTION:
XS GIS Cut Line= 3
      2738658.96     10155494.43      2739537.05     10155529.68
      2740205.71     10155753.12
#Sta/Elev= 30
  4121.2  1512.4    4228 1510.28  4308.1 1512.01  4358.1 1510.72  4457.7 1504.37
  4518.2 1502.36  4868.5 1504.24  4898.5 1499.74  4968.6 1497.07  4988.6 1493.64
  4994.1 1491.47  4994.5 1490.97  4999.5 1491.47  5009.1 1493.64  5019.6 1498.46
  5025.8 1499.88  5040.7 1497.37  5057.3 1492.63  5062.6    1493  5082.9 1497.99
  5094.2 1502.56    5104 1504.22  5146.2 1504.61  5183.7 1507.49  5246.9 1507.07
  5346.9  1510.3  5441.7  1511.6  5494.1 1514.35  5631.3 1526.61    5705 1529.61
#Mann= 3 ,-1 , 0
  4121.2     .05       0  4994.1     .05       0  4999.5     .05       0
Bank Sta=4994.1,4999.5
XS Rating Curve= 0 ,0
Exp/Cntr=0.3,0.1

Type RM Length L Ch R = 1 ,12500   ,352,352,352
BEGIN DESCRIPTION:
LITTLE COTTONWOOD CREEK 25.0
END DESCRIPTION:
XS GIS Cut Line= 3
      2738855.67     10155953.11        2739356.     10155987.34
      2739985.28     10156015.26
#Sta/Elev= 30
  4498.5 1512.33  4538.6 1510.17  4558.7 1508.05  4572.7 1508.15  4628.8 1504.65
  4658.9 1503.98    4689 1500.54  4716.2  1499.6  4729.1    1500  4839.3 1498.13
  4949.6  1499.4  4969.6 1498.99  4979.6 1497.21    4994 1489.24  4994.5 1488.74
  5000.6 1489.24  5016.1 1491.26  5021.1 1491.08  5039.7 1495.43  5049.7 1496.64
  5089.8 1498.73  5119.8 1501.29  5139.8  1501.3  5176.5 1503.48  5209.9 1504.37
    5244  1503.6  5299.6 1503.81  5510.2 1504.24  5560.2 1506.55  5629.9 1511.57
#Mann= 5 ,-1 , 0
  4498.5     .05       0    4994     .05       0  5000.6     .05       0
  5176.5     .12       0  5299.6     .05       0
Bank Sta=4994,5000.6
XS Rating Curve= 0 ,0
Exp/Cntr=0.3,0.1

Type RM Length L Ch R = 1 ,12148   ,726,726,726
BEGIN DESCRIPTION:
LITTLE COTTONWOOD CREEK 24.0
END DESCRIPTION:
XS GIS Cut Line= 3
      2738855.71     10156053.12       2739515.5       10156253.
       2740061.2     10156410.95
#Sta/Elev= 30
  4310.6 1512.47  4509.1 1506.32  4567.9  1501.4  4613.6 1504.26    4639 1503.11
  4644.9  1500.8  4665.8 1499.32  4671.9 1499.46  4677.1 1501.83  4697.2 1497.77
  4704.8 1492.85    4710 1493.83  4718.1 1490.82  4728.5 1494.99    4743 1494.44
  4808.8 1497.21  4841.7 1494.59  4846.9 1492.93  4912.8 1494.26  4950.9 1490.15
  5028.1 1487.68  5028.6 1487.18  5034.7 1487.68  5041.8 1488.17  5062.7 1500.22
  5304.3 1500.68  5379.1 1500.82  5482.2 1500.61  5490.4 1501.66  5568.1 1507.09
#Mann= 7 ,-1 , 0
  4310.6     .05       0  5028.1     .05       0  5034.7     .05       0
  5304.3     .12       0  5379.1     .05       0  5482.2     .12       0
  5490.4     .05       0
Bank Sta=5028.1,5034.7
XS Rating Curve= 0 ,0
Exp/Cntr=0.3,0.1

Type RM Length L Ch R = 1 ,11422   ,422,422,422
BEGIN DESCRIPTION:
LITTLE COTTONWOOD CREEK 23.0
END DESCRIPTION:
XS GIS Cut Line= 3
      2738867.25     10156605.54        2739404.       10156726.
      2739908.92     10156931.93
#Sta/Elev= 30
  4449.9    1499  4591.8 1502.84  4663.5  1503.2  4714.8  1499.9  4762.7 1493.11
  4781.3 1491.42  4858.2 1491.64  4873.1 1490.07  4950.5  1491.7  4981.2  1488.4
  4998.3 1485.27    5020 1484.52  5020.5 1484.02  5026.8 1484.52  5030.4 1490.39
    5045 1491.84  5183.6  1491.5  5228.6 1491.47  5273.8 1495.04  5380.8 1500.66
  5399.4 1500.31  5404.8 1501.41  5452.9  1500.8  5458.3 1501.93  5476.9 1500.37
  5487.8 1501.64  5506.4 1501.39  5511.8 1502.61  5530.4 1500.23  5545.3 1502.63
#Mann= 5 ,-1 , 0
  4449.9     .05       0  4762.7     .12       0    5020     .07       0
  5026.8     .12       0  5183.6     .05       0
Bank Sta=5020,5026.8
XS Rating Curve= 0 ,0
Exp/Cntr=0.3,0.1

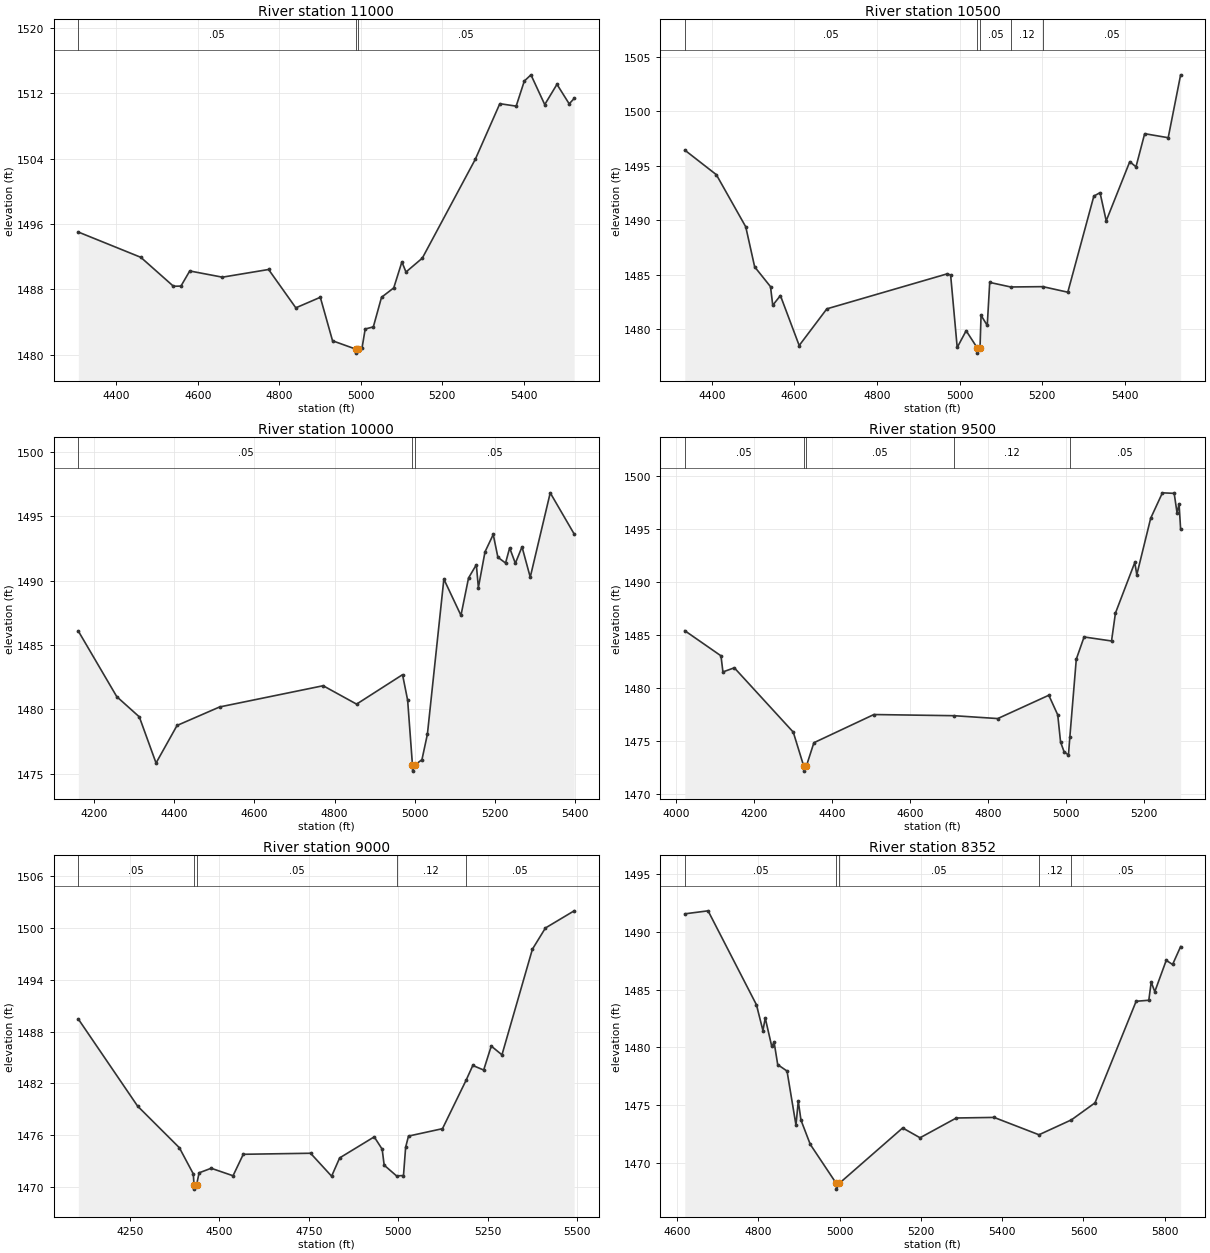
Type RM Length L Ch R = 1 ,11000   ,500,500,500
BEGIN DESCRIPTION:
LITTLE COTTONWOOD CREEK 22.0
END DESCRIPTION:
XS GIS Cut Line= 3
      2738582.57     10157140.26      2739274.78     10157107.26
      2739797.83     10157133.32
#Sta/Elev= 30
    4307 1495.02  4460.3 1491.93  4540.4 1488.39  4558.8 1488.41  4580.4 1490.26
  4660.5  1489.5  4773.9 1490.44  4840.7 1485.75  4900.8 1487.04  4930.8 1481.72
  4987.3 1480.71  4987.8 1480.21  4994.4 1480.71    5003 1480.78  5010.9 1483.16
  5030.9 1483.42    5051 1487.04    5081 1488.19    5101 1491.37    5111 1490.13
  5151.1 1491.83  5281.3 1503.94  5341.3 1510.72  5381.4 1510.42  5401.4 1513.49
  5417.7 1514.25  5451.5 1510.61  5481.5 1513.09  5511.5  1510.7  5523.7 1511.36
#Mann= 3 ,-1 , 0
    4307     .05       0  4987.3     .05       0  4994.4     .05       0
Bank Sta=4987.3,4994.4
XS Rating Curve= 0 ,0
Exp/Cntr=0.3,0.1

Type RM Length L Ch R = 1 ,10500   ,500,500,500
BEGIN DESCRIPTION:
LITTLE COTTONWOOD CREEK 21.0
END DESCRIPTION:
XS GIS Cut Line= 3
      2738718.86      10157766.5       2739335.7     10157515.89
      2739781.23     10157218.45
#Sta/Elev= 30
  4334.2 1496.45  4410.7 1494.19  4481.9  1489.4  4503.5 1485.72  4541.9  1483.9
  4547.3 1482.19  4565.9 1483.08  4611.4 1478.49  4678.4 1481.86  4970.3 1485.08
  4978.4 1484.96  4994.3 1478.31    5016 1479.85  5042.5 1478.29    5043 1477.79
  5049.6 1478.29  5052.1 1481.27  5067.1 1480.33  5073.1 1484.29    5124 1483.87
  5201.9  1483.9  5262.3 1483.39  5325.4 1492.22  5340.4 1492.54  5355.4 1489.95
  5412.5 1495.39  5427.5 1494.91  5448.6 1497.96  5505.6 1497.59  5535.7 1503.37
#Mann= 5 ,-1 , 0
  4334.2     .05       0  5042.5     .05       0  5049.6     .05       0
    5124     .12       0  5201.9     .05       0
Bank Sta=5042.5,5049.6
XS Rating Curve= 0 ,0
Exp/Cntr=0.3,0.1

Type RM Length L Ch R = 1 ,10000   ,500,500,500
BEGIN DESCRIPTION:
LITTLE COTTONWOOD CREEK 20.0
END DESCRIPTION:
XS GIS Cut Line= 3
      2738929.73       10157925.      2739735.01     10157692.37
      2740122.48     10157605.93
#Sta/Elev= 30
  4161.8 1486.08  4257.6 1480.98  4313.7 1479.41  4355.4 1475.82  4407.7 1478.74
  4513.8 1480.18  4771.7 1481.83    4855  1480.4  4969.5 1482.69  4982.2  1480.7
  4994.1 1475.69  4994.6 1475.19  5001.3 1475.69  5017.8 1476.08  5031.4 1478.06
  5072.4 1490.12    5115  1487.3  5133.9 1490.21  5153.3 1491.24  5158.4 1489.46
  5174.9 1492.24  5195.4 1493.59    5207 1491.82  5226.1 1491.37  5236.3 1492.55
  5250.5 1491.35  5267.1 1492.63  5287.6 1490.27  5337.4 1496.83    5397 1493.63
#Mann= 3 ,-1 , 0
  4161.8     .05       0  4994.1     .03       0  5001.3     .05       0
Bank Sta=4994.1,5001.3
XS Rating Curve= 0 ,0
Exp/Cntr=0.3,0.1

Type RM Length L Ch R = 1 ,9500    ,500,500,500
BEGIN DESCRIPTION:
LITTLE COTTONWOOD CREEK 19.0
END DESCRIPTION:
XS GIS Cut Line= 3
      2738929.77      10158036.1      2739898.75     10158161.02
      2740192.14     10158188.73
#Sta/Elev= 30
    4023 1485.39  4115.8 1483.02  4120.8  1481.5    4150 1481.89  4301.2 1475.82
  4327.8 1472.64  4328.3 1472.14    4335 1472.64  4354.1 1474.82    4508 1477.48
  4713.6 1477.37  4825.7  1477.1  4956.6  1479.3  4979.5 1477.45  4986.8 1474.88
  4995.9 1473.96    5007 1473.66  5010.6 1475.37  5027.1  1482.7  5047.1  1484.8
  5117.5 1484.42  5127.5 1487.05  5177.2 1491.83  5182.3 1490.67  5217.9    1496
    5248  1498.4  5278.2 1498.35  5285.6 1496.49  5290.7 1497.37  5294.7 1494.97
#Mann= 5 ,-1 , 0
    4023     .05       0  4327.8     .07       0    4335     .05       0
  4713.6     .12       0  5010.6     .05       0
Bank Sta=4327.8,4335
XS Rating Curve= 0 ,0
Exp/Cntr=0.3,0.1

Type RM Length L Ch R = 1 ,9000    ,648,648,648
BEGIN DESCRIPTION:
LITTLE COTTONWOOD CREEK 18.0
END DESCRIPTION:
XS GIS Cut Line= 3
      2738895.01     10158181.92      2739691.37     10158587.96
      2740105.69     10158853.11
#Sta/Elev= 30
  4106.1 1489.46  4271.7 1479.37  4388.5 1474.54  4427.4 1471.51  4429.4 1470.24
  4429.9 1469.74  4436.6 1470.24  4443.6 1471.63  4477.4 1472.16  4538.5 1471.29
  4567.1 1473.78  4755.2  1473.9    4814 1471.24  4836.5 1473.36  4933.1  1475.8
  4955.3 1474.37  4960.9 1472.52  4995.6 1471.27  5014.9 1471.32  5020.9  1474.6
  5028.9 1475.89  5123.9 1476.75  5189.8 1482.36  5208.6 1484.08    5239 1483.55
  5260.2 1486.33  5290.1 1485.31  5375.2 1497.56  5411.6 1500.02  5491.9 1502.01
#Mann= 5 ,-1 , 0
  4106.1     .05       0  4429.4     .07       0  4436.6     .05       0
  4995.6     .12       0  5189.8     .05       0
Bank Sta=4429.4,4436.6
XS Rating Curve= 0 ,0
Exp/Cntr=0.3,0.1

Type RM Length L Ch R = 1 ,8352    ,352,352,352
BEGIN DESCRIPTION:
LITTLE COTTONWOOD CREEK 17.0
END DESCRIPTION:
XS GIS Cut Line= 3
      2738805.65     10158353.09        2739139.       10158538.
      2739860.34     10158966.67
#Sta/Elev= 30
  4618.8 1491.55  4676.1 1491.81  4795.1 1483.69  4811.1 1481.46  4816.8 1482.54
  4832.8 1480.09  4838.6 1480.45  4847.5 1478.51  4870.4 1477.96  4892.4 1473.29
  4898.1 1475.36  4904.7 1473.72  4927.6 1471.62  4991.5 1468.25    4992 1467.75
    4999 1468.25    5155 1473.04  5197.8 1472.19    5287  1473.9    5380 1473.95
  5490.5 1472.45  5570.4 1473.74  5628.4 1475.21  5729.6 1483.99  5760.8 1484.08
  5766.7 1485.65  5775.5 1484.82  5803.7 1487.53  5819.3 1487.17  5839.1 1488.72
#Mann= 5 ,-1 , 0
  4618.8     .05       0  4991.5     .03       0    4999     .05       0
  5490.5     .12       0  5570.4     .05       0
Bank Sta=4991.5,4999
XS Rating Curve= 0 ,0
Exp/Cntr=0.3,0.1