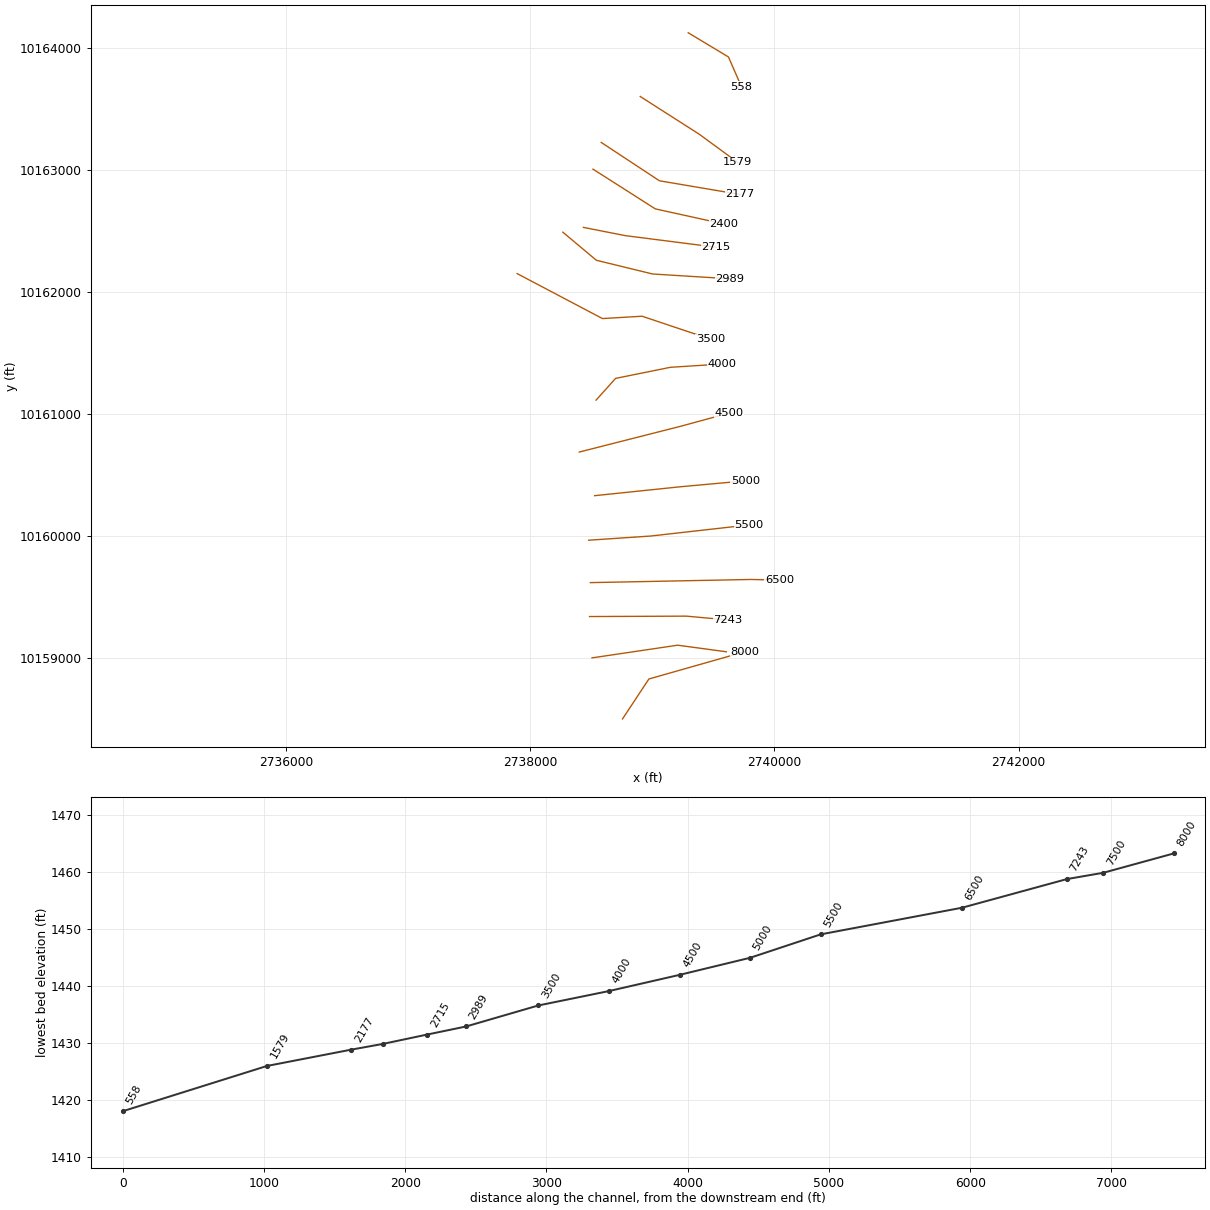
HEC-RAS study LITTLE COTTONWOOD CREEK.prj: LITTLE COTTONWOOD CREEK Base Level Engineering

--- LITTLE COTTONWOOD CREEK.g01 (geometry) --- (continued)

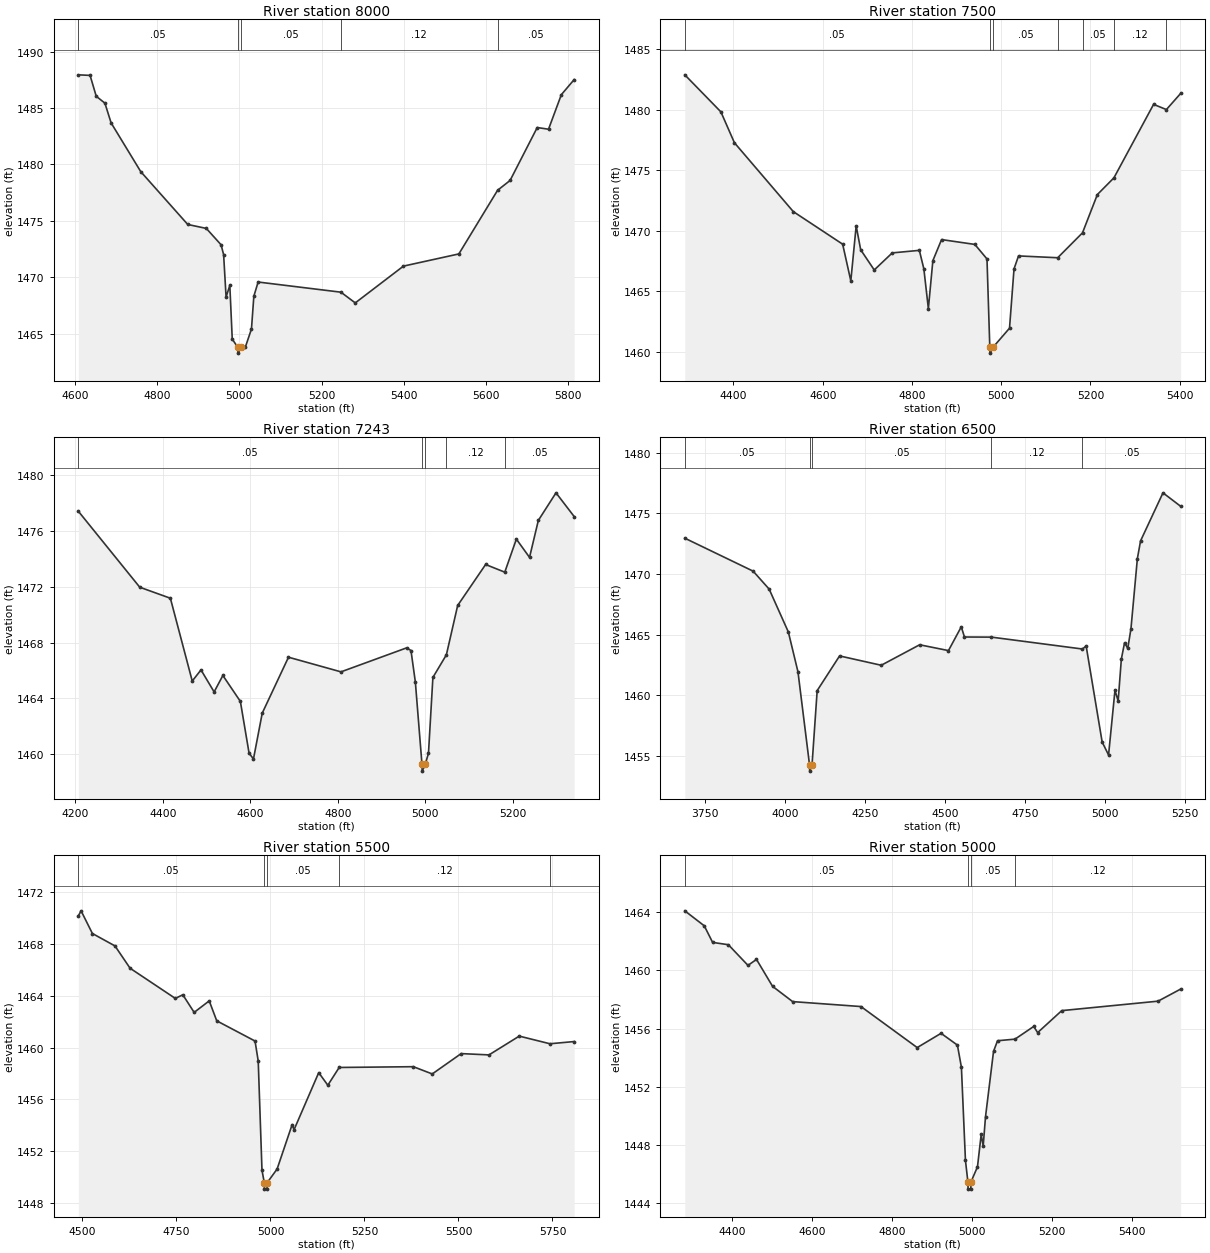
Type RM Length L Ch R = 1 ,8000    ,500,500,500
BEGIN DESCRIPTION:
LITTLE COTTONWOOD CREEK 16.0
END DESCRIPTION:
XS GIS Cut Line= 3
      2738755.69     10158503.12      2738971.69     10158830.24
      2739755.72     10159053.12
#Sta/Elev= 30
    4608 1487.94  4636.6 1487.89  4651.6 1486.04  4672.7 1485.43  4687.8 1483.68
    4760 1479.36  4874.4 1474.68  4919.6 1474.33  4955.5 1472.88  4961.7 1472.01
  4967.7 1468.25  4976.8 1469.28  4982.7 1464.53  4996.3 1463.78  4996.8 1463.28
  5003.8 1463.78  5014.5  1463.8  5029.5 1465.42  5035.3 1468.32  5045.7 1469.58
  5247.3 1468.68  5282.2 1467.73  5399.5 1470.99  5534.4 1472.07  5628.7 1477.71
  5659.1 1478.58  5725.2 1483.27  5752.7 1483.12  5783.9 1486.18  5815.1 1487.52
#Mann= 5 ,-1 , 0
    4608     .05       0  4996.3     .03       0  5003.8     .05       0
  5247.3     .12       0  5628.7     .05       0
Bank Sta=4996.3,5003.8
XS Rating Curve= 0 ,0
Exp/Cntr=0.3,0.1

Type RM Length L Ch R = 1 ,7500    ,257,257,257
BEGIN DESCRIPTION:
LITTLE COTTONWOOD CREEK 15.0
END DESCRIPTION:
XS GIS Cut Line= 3
       2738505.7     10159003.11      2739207.14     10159107.04
      2739605.71     10159053.11
#Sta/Elev= 30
  4290.9 1482.87  4371.8 1479.81  4402.1 1477.26  4534.1 1471.57  4644.7 1468.88
    4663 1465.85    4675 1470.39  4685.1 1468.42  4715.5 1466.75  4755.9 1468.16
  4816.6 1468.37  4826.7 1466.84  4836.8 1463.56  4846.9 1467.52  4866.4 1469.26
    4941 1468.86  4968.2 1467.66  4974.5 1460.38    4975 1459.88  4982.1 1460.38
  5018.7 1461.94  5028.8 1466.84  5038.9 1467.91  5126.7 1467.76  5182.3 1469.82
  5215.6 1472.98  5252.7 1474.36  5341.6 1480.43  5370.3    1480  5402.2 1481.33
#Mann= 7 ,-1 , 0
  4290.9     .05       0  4974.5     .05       0  4982.1     .05       0
  5126.7     .12       0  5182.3     .05       0  5252.7     .12       0
  5370.3     .05       0
Bank Sta=4974.5,4982.1
XS Rating Curve= 0 ,0
Exp/Cntr=0.3,0.1

Type RM Length L Ch R = 1 ,7243    ,743,743,743
BEGIN DESCRIPTION:
LITTLE COTTONWOOD CREEK 14.0
END DESCRIPTION:
XS GIS Cut Line= 3
      2738485.31     10159341.65       2739278.5       10159345.
      2739617.27     10159313.88
#Sta/Elev= 30
  4206.8 1477.42  4347.2 1471.97  4417.2 1471.18  4467.2 1465.24  4487.2 1466.04
  4517.2 1464.46  4537.2 1465.64  4577.2 1463.78  4597.2 1460.05  4607.2 1459.66
  4627.2 1462.94  4687.2 1466.95  4807.2  1465.9  4957.2 1467.62  4967.2 1467.43
  4977.2 1465.17  4992.3 1459.28  4992.8 1458.78  4999.9 1459.28  5007.2 1460.06
  5017.3  1465.5  5048.1 1467.12  5073.9 1470.66  5137.8  1473.6  5181.6 1473.05
  5208.1 1475.42  5238.2 1474.11  5258.3 1476.76  5298.7 1478.74  5340.2 1477.04
#Mann= 5 ,-1 , 0
  4206.8     .05       0  4992.3     .05       0  4999.9     .05       0
  5048.1     .12       0  5181.6     .05       0
Bank Sta=4992.3,4999.9
XS Rating Curve= 0 ,0
Exp/Cntr=0.3,0.1

Type RM Length L Ch R = 1 ,6500    ,1000,1000,1000
BEGIN DESCRIPTION:
LITTLE COTTONWOOD CREEK 13.0
END DESCRIPTION:
XS GIS Cut Line= 3
      2738492.24     10159619.43      2739804.79     10159645.23
      2740040.74     10159640.27
#Sta/Elev= 30
  3687.2 1472.96  3900.7 1470.24  3950.7 1468.76  4010.7 1465.22  4040.7 1461.94
  4076.9 1454.25  4077.4 1453.75  4084.6 1454.25  4100.7 1460.39  4170.7 1463.25
  4300.8 1462.48  4420.8 1464.17  4510.8 1463.69  4550.8 1465.65  4560.8 1464.81
  4645.2  1464.8  4929.3 1463.82  4940.9 1464.07  4990.9 1456.15  5010.9 1455.08
  5030.9 1460.41  5040.9 1459.54  5050.9    1463  5060.9 1464.34  5070.9 1463.87
  5080.9  1465.5  5100.9 1471.28  5110.9 1472.74  5180.9  1476.7    5236 1475.59
#Mann= 5 ,-1 , 0
  3687.2     .05       0  4076.9     .03       0  4084.6     .05       0
  4645.2     .12       0  4929.3     .05       0
Bank Sta=4076.9,4084.6
XS Rating Curve= 0 ,0
Exp/Cntr=0.3,0.1

Type RM Length L Ch R = 1 ,5500    ,500,500,500
BEGIN DESCRIPTION:
LITTLE COTTONWOOD CREEK 11.0
END DESCRIPTION:
XS GIS Cut Line= 3
      2738478.39     10159966.66      2738988.23     10160001.12
      2739790.74     10160091.64
#Sta/Elev= 30
    4489 1470.17  4496.3 1470.56  4526.4 1468.81  4586.5 1467.85  4626.6 1466.13
  4746.9  1463.8  4766.9 1464.08    4797 1462.72  4837.1 1463.61  4857.1 1462.07
  4958.9 1460.51  4967.4 1458.97  4977.4 1450.54  4983.5 1449.58    4984 1449.08
  4990.8 1449.08  4991.3 1449.58  5017.6 1450.63  5057.6 1454.06  5062.6 1453.66
  5128.3 1458.07  5152.5  1457.1  5182.7 1458.47  5379.9 1458.53  5430.2 1457.97
  5507.1 1459.54  5581.1 1459.44  5661.6 1460.89  5743.2  1460.3  5807.6 1460.47
#Mann= 5 ,-1 , 0
    4489     .05       0  4983.5     .05       0  4991.3     .05       0
  5182.7     .12       0  5743.2     .05       0
Bank Sta=4983.5,4991.3
XS Rating Curve= 0 ,0
Exp/Cntr=0.3,0.1

Type RM Length L Ch R = 1 ,5000    ,500,500,500
BEGIN DESCRIPTION:
LITTLE COTTONWOOD CREEK 10.0
END DESCRIPTION:
XS GIS Cut Line= 3
      2738527.29     10160331.35      2739241.34     10160405.59
      2739761.91     10160452.66
#Sta/Elev= 30
  4282.1  1464.1  4330.8 1463.07  4351.7 1461.93  4391.1 1461.77  4440.2 1460.35
  4461.5 1460.76  4501.7 1458.91  4551.9 1457.86  4722.9 1457.52  4863.6  1454.7
  4923.3 1455.68  4964.2 1454.87  4974.2 1453.35  4984.3 1446.95  4990.4 1445.47
  4990.9 1444.97  4997.7 1444.97  4998.2 1445.47  5014.4  1446.5  5023.7 1448.73
  5028.7 1447.93  5034.5 1449.94  5054.6 1454.44  5064.6 1455.17  5108.3 1455.28
    5155 1456.15    5165 1455.73  5225.3 1457.24  5466.2 1457.89  5522.7 1458.72
#Mann= 4 ,-1 , 0
  4282.1     .05       0  4990.4     .05       0  4998.2     .05       0
  5108.3     .12       0
Bank Sta=4990.4,4998.2
XS Rating Curve= 0 ,0
Exp/Cntr=0.3,0.1

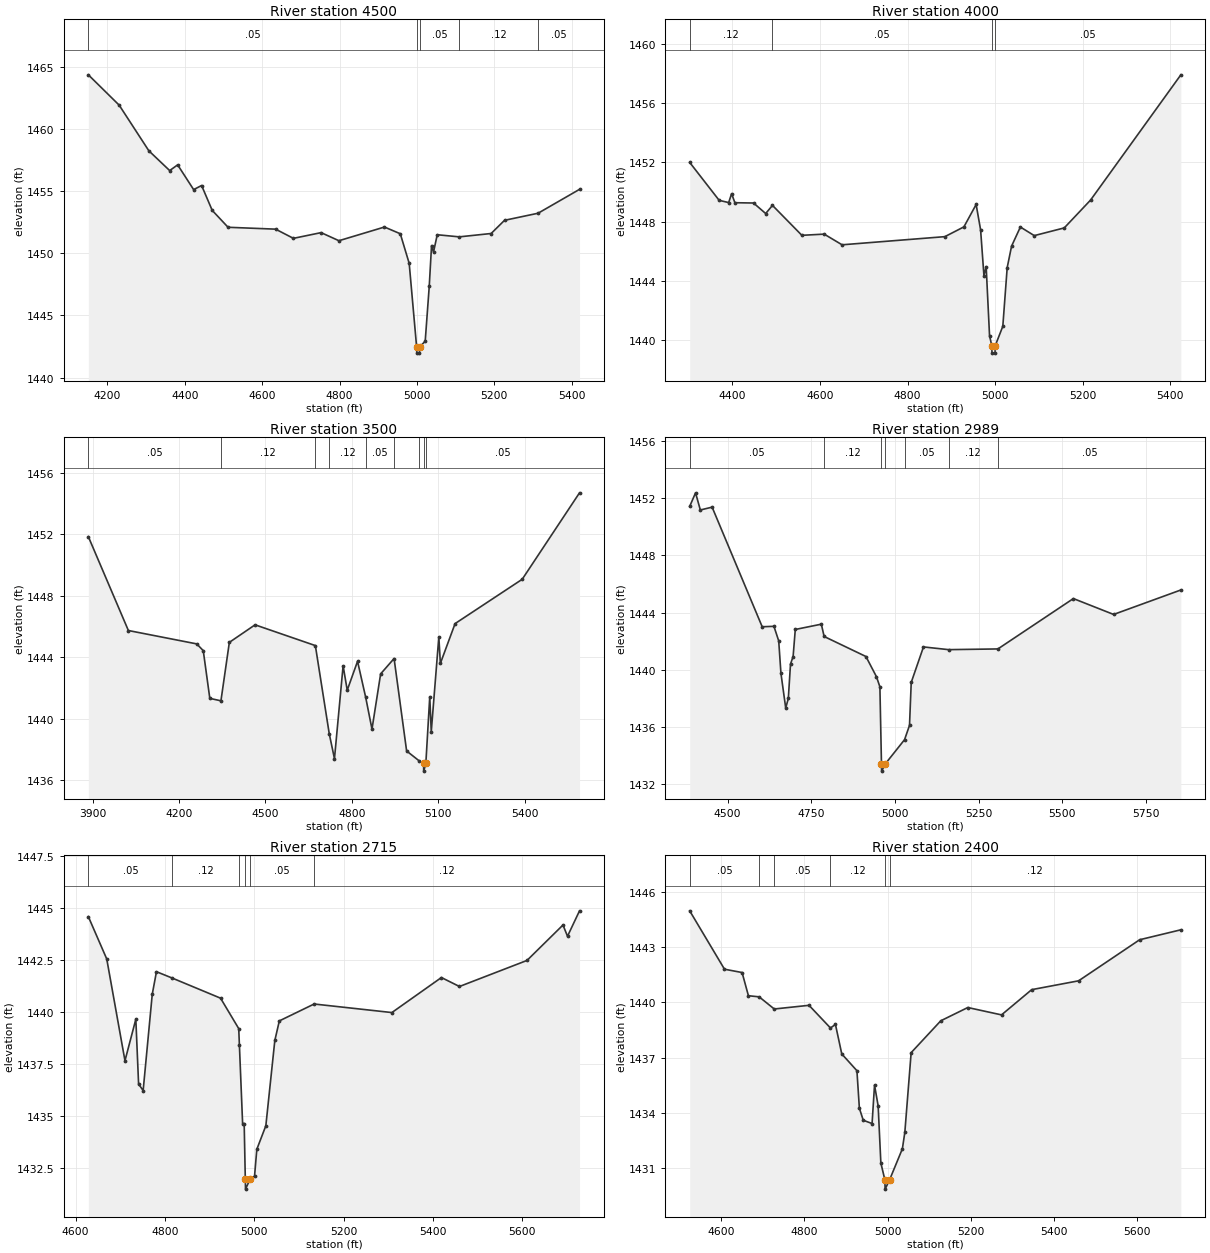
Type RM Length L Ch R = 1 ,4500    ,500,500,500
BEGIN DESCRIPTION:
LITTLE COTTONWOOD CREEK 9.0
END DESCRIPTION:
XS GIS Cut Line= 3
      2738401.98     10160688.88      2739224.93     10160897.98
      2739630.53     10161008.15
#Sta/Elev= 30
  4150.9 1464.35  4230.6 1461.91  4307.3 1458.24  4361.1 1456.65  4381.7 1457.11
    4423 1455.12  4443.6 1455.45    4471 1453.45    4512 1452.09  4634.8 1451.94
  4680.9  1451.2  4752.4 1451.66  4798.5 1451.01  4916.2 1452.11  4957.1 1451.57
  4980.1 1449.19  4999.3 1442.47  4999.8 1441.97  5006.7 1441.97  5007.2 1442.47
  5021.5 1442.93  5031.9 1447.33  5037.9 1450.62    5043  1450.1  5052.6 1451.49
  5109.5 1451.32  5191.9 1451.59  5226.5 1452.65  5313.2 1453.22  5420.3 1455.14
#Mann= 5 ,-1 , 0
  4150.9     .05       0  4999.3     .05       0  5007.2     .05       0
  5109.5     .12       0  5313.2     .05       0
Bank Sta=4999.3,5007.2
XS Rating Curve= 0 ,0
Exp/Cntr=0.3,0.1

Type RM Length L Ch R = 1 ,4000    ,500,500,500
BEGIN DESCRIPTION:
LITTLE COTTONWOOD CREEK 8.0
END DESCRIPTION:
XS GIS Cut Line= 4
       2738539.4     10161113.93      2738698.83     10161291.88
      2739148.32     10161382.71      2739571.38     10161409.41
#Sta/Elev= 30
  4302.5    1452  4369.8 1449.44  4391.5 1449.29  4398.2 1449.89  4405.7 1449.28
  4448.3 1449.26    4476 1448.55  4491.5  1449.1  4558.6 1447.08  4609.6 1447.16
  4650.4 1446.44  4885.1 1446.99  4928.6 1447.65  4956.5 1449.16  4966.7 1447.45
  4974.3 1444.36  4979.4 1444.97  4987.1 1440.31  4992.2 1439.63  4992.7 1439.13
  4999.6 1439.13  5000.1 1439.63  5017.4 1440.94  5027.4  1444.9  5037.4 1446.35
  5057.5 1447.64  5089.2 1447.06  5157.7 1447.58  5217.8 1449.46  5423.9 1457.91
#Mann= 4 ,-1 , 0
  4302.5     .12       0  4491.5     .05       0  4992.2     .05       0
  5000.1     .05       0
Bank Sta=4992.2,5000.1
XS Rating Curve= 0 ,0
Exp/Cntr=0.3,0.1

Type RM Length L Ch R = 1 ,3500    ,511,511,511
BEGIN DESCRIPTION:
LITTLE COTTONWOOD CREEK 7.0
END DESCRIPTION:
XS GIS Cut Line= 4
      2737892.84     10162149.97      2738591.53     10161781.72
      2738915.77     10161800.95      2739475.11     10161613.55
#Sta/Elev= 30
  3885.4 1451.84  4024.3 1445.74  4261.6 1444.87  4284.2 1444.43  4306.9 1441.33
  4345.5 1441.17  4374.7 1444.97    4464 1446.11  4673.2 1444.76  4721.5 1439.02
  4739.5 1437.41  4769.5 1443.45  4783.8 1441.86  4819.6 1443.74  4847.7 1441.41
  4869.7 1439.33  4899.7 1442.92  4946.4 1443.92  4989.9 1437.91  5032.6 1437.28
  5048.7  1437.1  5049.2  1436.6  5056.6  1437.1  5070.2 1441.44  5075.4 1439.16
  5101.7 1445.33    5107  1443.6  5158.1 1446.19    5391 1449.07  5589.9 1454.69
#Mann= 9 ,-1 , 0
  3885.4     .05       0  4345.5     .12       0  4673.2     .05       0
  4721.5     .12       0  4847.7     .05       0  4946.4     .12       0
  5032.6     .05       0  5048.7     .07       0  5056.6     .05       0
Bank Sta=5048.7,5056.6
XS Rating Curve= 0 ,0
Exp/Cntr=0.3,0.1

Type RM Length L Ch R = 1 ,2989    ,274,274,274
BEGIN DESCRIPTION:
Mapping XS b4c02c8f
END DESCRIPTION:
XS GIS Cut Line= 4
      2738266.96      10162489.1      2738541.92     10162259.03
      2739002.07      10162146.8       2739636.2     10162107.52
#Sta/Elev= 30
  4386.5 1451.42    4404 1452.37  4418.3 1451.17  4453.5 1451.37  4603.1 1443.01
  4638.2 1443.04  4652.5 1442.02  4659.1 1439.76  4673.4 1437.33  4681.2    1438
  4687.7  1440.4  4695.5 1440.93    4702 1442.82  4779.8 1443.19  4788.2 1442.33
  4913.1 1440.93  4944.5 1439.52  4954.8 1438.81  4959.5 1433.42    4960 1432.92
  4970.7 1433.42  5028.5 1435.12  5043.3 1436.12  5048.4 1439.12    5085  1441.6
  5160.1 1441.41  5307.4 1441.46  5532.9 1444.98  5653.1 1443.87    5854 1445.58
#Mann= 7 ,-1 , 0
  4386.5     .05       0  4788.2     .12       0  4959.5     .07       0
  4970.7     .12       0  5028.5     .05       0  5160.1     .12       0
  5307.4     .05       0
Bank Sta=4959.5,4970.7
XS Rating Curve= 0 ,0
Exp/Cntr=0.3,0.1

Type RM Length L Ch R = 1 ,2715    ,315,315,315
BEGIN DESCRIPTION:
Mapping XS 7a29ade5
END DESCRIPTION:
XS GIS Cut Line= 3
      2738435.27     10162528.39       2738777.6     10162461.05
      2739522.35     10162365.86
#Sta/Elev= 30
  4628.5 1444.58  4669.7 1442.55  4710.5 1437.67  4734.8 1439.66    4741 1436.55
  4751.2 1436.24  4771.6 1440.86    4781 1441.94  4816.8 1441.63  4924.5 1440.67
  4965.2 1439.21  4966.7 1438.42  4973.9 1434.65  4977.4 1434.65  4979.9 1432.01
  4980.4 1431.51  4991.1 1432.01  5000.6 1432.13  5005.7 1433.42  5025.9 1434.55
    5046 1438.64  5056.1 1439.58    5134 1440.39  5308.1 1439.98    5419 1441.66
  5459.4 1441.23  5610.6 1442.48  5691.2 1444.18  5701.3 1443.64  5728.2 1444.86
#Mann= 6 ,-1 , 0
  4628.5     .05       0  4816.8     .12       0  4966.7     .05       0
  4979.9     .05       0  4991.1     .05       0    5134     .12       0
Bank Sta=4979.9,4991.1
XS Rating Curve= 0 ,0
Exp/Cntr=0.3,0.1

Type RM Length L Ch R = 1 ,2400    ,223,223,223
BEGIN DESCRIPTION:
Mapping XS 18eb7880
END DESCRIPTION:
XS GIS Cut Line= 3
      2738513.88     10163005.36      2739024.51      10162679.9
      2739585.67     10162556.45
#Sta/Elev= 30
  4524.3 1444.97  4607.9  1441.8  4650.2 1441.62  4665.4 1440.36  4691.2  1440.3
  4727.5 1439.64    4811 1439.84  4862.5 1438.61  4874.5  1438.8  4889.7  1437.2
  4926.1 1436.29    4932 1434.25  4941.3  1433.6  4962.5 1433.42  4968.4 1435.51
  4977.1 1434.38  4983.6 1431.28  4993.3 1430.36  4993.8 1429.86  5004.5 1430.36
  5035.3 1432.05  5041.2 1432.94  5056.4 1437.27  5127.6    1439  5192.5 1439.72
  5273.5 1439.32    5346 1440.69  5458.7 1441.17  5605.4  1443.4  5704.4 1443.94
#Mann= 6 ,-1 , 0
  4524.3     .05       0  4691.2     .12       0  4727.5     .05       0
  4862.5     .12       0  4993.3     .07       0  5004.5     .12       0
Bank Sta=4993.3,5004.5
XS Rating Curve= 0 ,0
Exp/Cntr=0.3,0.1

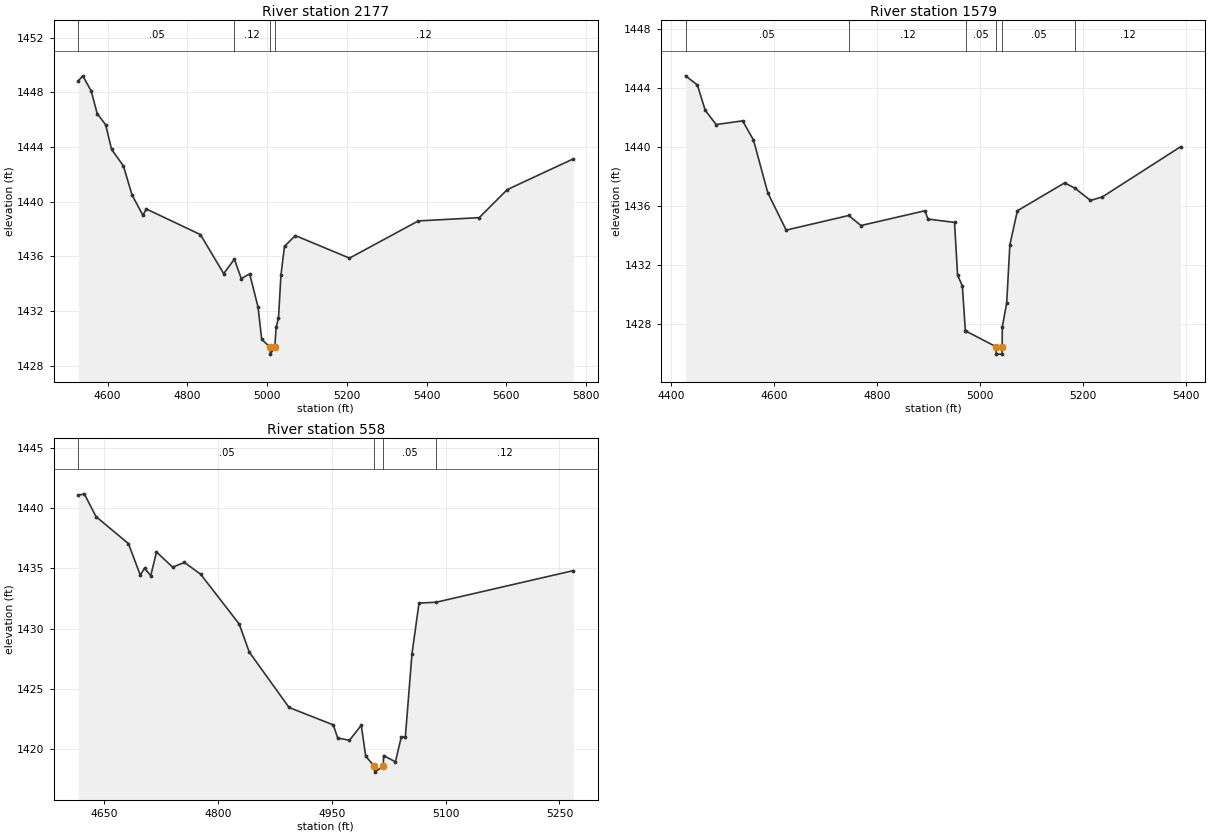
Type RM Length L Ch R = 1 ,2177    ,598,598,598
BEGIN DESCRIPTION:
Mapping XS e8c7a837
END DESCRIPTION:
XS GIS Cut Line= 3
      2738581.19     10163224.23      2739058.18     10162909.98
      2739719.25     10162797.93
#Sta/Elev= 30
  4526.6 1448.84  4537.8 1449.21  4558.9 1448.11    4574 1446.44  4595.1 1445.64
  4610.1 1443.83  4639.8 1442.62  4661.3 1440.51  4688.4 1439.02  4697.5 1439.47
    4833  1437.6  4891.2 1434.75  4918.1  1435.8  4935.4 1434.38  4956.4 1434.73
  4977.5 1432.29  4986.6 1429.94  5007.8 1429.36  5008.3 1428.86  5019.5 1429.36
  5022.7 1430.81  5028.7 1431.49  5034.9 1434.65  5043.8 1436.74  5070.9 1437.53
  5206.8 1435.88  5379.3  1438.6  5532.2 1438.84  5602.4 1440.89  5768.3 1443.14
#Mann= 4 ,-1 , 0
  4526.6     .05       0  4918.1     .12       0  5007.8     .07       0
  5019.5     .12       0
Bank Sta=5007.8,5019.5
XS Rating Curve= 0 ,0
Exp/Cntr=0.3,0.1

Type RM Length L Ch R = 1 ,1579    ,1021,1021,1021
BEGIN DESCRIPTION:
Mapping XS a2a313b8
END DESCRIPTION:
XS GIS Cut Line= 3
      2738901.02     10163600.22      2739383.65     10163291.56
      2739697.93     10163061.47
#Sta/Elev= 30
  4427.4 1444.84  4450.3 1444.22  4465.5 1442.51  4486.7 1441.54  4538.3 1441.79
  4559.4 1440.49  4587.2 1436.92  4622.9 1434.39  4744.5 1435.38  4768.3  1434.7
  4892.6  1435.7  4898.6 1435.14  4950.2 1434.91  4956.1 1431.35  4965.4  1430.6
  4971.3 1427.55    4973 1427.54    5031 1426.49  5031.5 1425.99  5042.3 1425.99
  5042.8 1426.49  5043.1 1427.84  5051.6 1429.45  5057.8  1433.4  5072.4  1435.7
  5164.3 1437.59  5184.3 1437.23  5214.5  1436.4  5237.6 1436.64  5389.8 1440.04
#Mann= 6 ,-1 , 0
  4427.4     .05       0  4744.5     .12       0    4973     .05       0
    5031     .05       0  5042.8     .05       0  5184.3     .12       0
Bank Sta=5031,5042.8
XS Rating Curve= 0 ,0
Exp/Cntr=0.3,0.1

Type RM Length L Ch R = 1 ,558     ,0,0,0
BEGIN DESCRIPTION:
LITTLE COTTONWOOD CREEK 6.0
END DESCRIPTION:
XS GIS Cut Line= 3
      2739293.83      10164122.1      2739623.25       10163924.
      2739730.67     10163678.14
#Sta/Elev= 30
  4615.6 1441.09  4623.5 1441.21    4639 1439.31  4681.7 1437.07  4697.3 1434.45
  4703.1 1435.04  4711.1 1434.39  4718.7 1436.37    4740 1435.11  4755.6  1435.5
  4776.9 1434.52  4827.8 1430.37    4841 1428.04  4893.5 1423.43  4951.8 1421.98
  4957.6 1420.89  4973.1  1420.7  4988.7 1421.95  4994.5 1419.37  5005.9 1418.55
  5006.4 1418.05  5017.8 1418.55    5018 1419.43  5033.7 1418.91  5041.4 1420.97
  5046.8 1420.98  5055.5 1427.88  5064.8 1432.12  5087.5 1432.19  5268.3 1434.82
#Mann= 4 ,-1 , 0
  4615.6     .05       0  5005.9     .03       0  5017.8     .05       0
  5087.5     .12       0
Bank Sta=5005.9,5017.8
XS Rating Curve= 0 ,0
Exp/Cntr=0.3,0.1
Stream Node=LITTLE COTTONWOO,Reach-1         , 0 , 0 ,Upstream end
Stream Node=LITTLE COTTONWOO,Reach-1         , 0 , 1 ,Downstream end

Chan Stop Cuts=-1
Use User Specified Reach Order=0
Composite Channel Slope=5