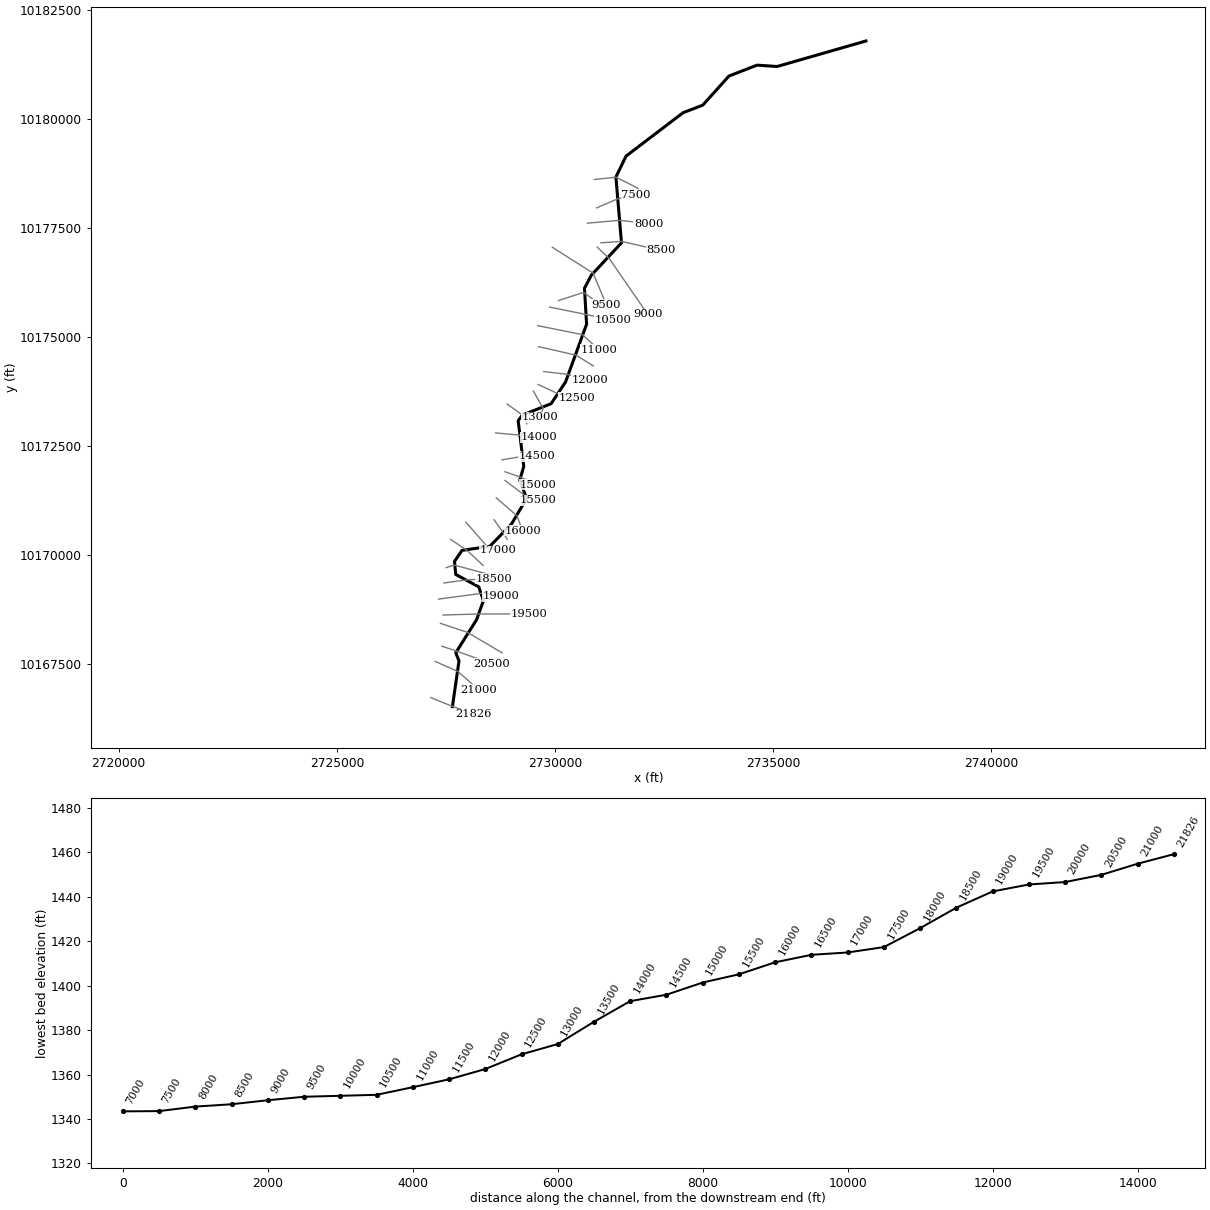
--- MARSCHALL BRANCH.prj (project) ---

Proj Title=MARSCHALL BRANCH Base Level Engineering
Current Plan=p01
Default Exp/Contr=0.3,0.1
English Units
Geom File=g01
Flow File=f01
Plan File=p01
Y Axis Title=Elevation
X Axis Title(PF)=Main Channel Distance
X Axis Title(XS)=Station
BEGIN DESCRIPTION:
MARSCHALL BRANCH
END DESCRIPTION:
DSS Export Rating Curves= 0
DSS Export Rating Curve Sorted= 0
DSS Export Volume Flow Curves= 0
DXF OffsetX= 0
DXF OffsetY= 0
DXF ScaleX= 1
DXF ScaleY= 10

--- MARSCHALL BRANCH.p01 (plan) ---

Plan Title=Multiple Run
Short Identifier=Multiple
Geom File=g01
Flow File=f01
Subcritical Flow
K Sum by GR= 0
Std Step Tol= 0.01
Critical Tol= 0.01
Num of Std Step Trials= 20
Max Error Tol= 0.3
Flow Tol Ratio= 0.001
Split Flow NTrial= 30
Split Flow Tol= 0.02
Split Flow Ratio= 0.02
Log Output Level= 0
Friction Slope Method= 1
Unsteady Friction Slope Method= 2
Unsteady Bridges Friction Slope Method= 1
Parabolic Critical Depth
Global Vel Dist=  1 , 1 , 1
Global Log Level= 0
CheckData=True
Encroach Param= -1, 0, 0, 0
BEGIN DESCRIPTION:
Multiple Run
END DESCRIPTION:

--- MARSCHALL BRANCH.f01 (steady flow) ---

Flow Title=Multiple
Program Version=4.10
Number of Profiles= 7
Profile Names=10-year,25-year,50-year,1pct_min,100-year,1pct_plu,500-year
River Rch & RM=MARSCHALL BRANCH,Reach-1         ,21826
    6313   12105   20541   13036   30017   69122   40720
River Rch & RM=MARSCHALL BRANCH,Reach-1         ,17500
    8618   16492   27643   17340   40202   93209   53957
River Rch & RM=MARSCHALL BRANCH,Reach-1         ,9500
   10141   19329   31884   24517   46134   86809   61435
River Rch & RM=MARSCHALL BRANCH,Reach-1         ,6000
   10321   19669   32404   24911   46879   88221   62401
River Rch & RM=MARSCHALL BRANCH,Reach-1         ,3500
   15155   28536   45514   34078   65055  124191   85258
River Rch & RM=MARSCHALL BRANCH,Reach-1         ,578
   15278   28766   45885   34340   65585  125260   85952
Boundary for River Rch & Prof#=MARSCHALL BRANCH,Reach-1         , 1
Up Type= 0
Dn Type= 3
Dn Slope=0.001
Boundary for River Rch & Prof#=MARSCHALL BRANCH,Reach-1         , 2
Up Type= 0
Dn Type= 3
Dn Slope=0.001
Boundary for River Rch & Prof#=MARSCHALL BRANCH,Reach-1         , 3
Up Type= 0
Dn Type= 3
Dn Slope=0.001
Boundary for River Rch & Prof#=MARSCHALL BRANCH,Reach-1         , 4
Up Type= 0
Dn Type= 3
Dn Slope=0.001
Boundary for River Rch & Prof#=MARSCHALL BRANCH,Reach-1         , 5
Up Type= 0
Dn Type= 3
Dn Slope=0.001
Boundary for River Rch & Prof#=MARSCHALL BRANCH,Reach-1         , 6
Up Type= 0
Dn Type= 3
Dn Slope=0.001
Boundary for River Rch & Prof#=MARSCHALL BRANCH,Reach-1         , 7
Up Type= 0
Dn Type= 3
Dn Slope=0.001
DSS Import GetInterval= 0
DSS Import GetPeak= 0
DSS Import FillOption= 0

--- MARSCHALL BRANCH.g01 (geometry) ---

Geom Title=Existing Conditions
Program Version=4.10

River Reach=MARSCHALL BRANCH,Reach-1
Reach XY= 30
        2727650.       10166517.        2727801.       10167567.
        2727726.       10167751.      2728204.25       10168511.
       2728360.5       10168945.      2728254.25       10169264.
        2727726.       10169548.        2727698.       10169848.
        2727871.       10170100.      2728508.25       10170194.
      2729004.25       10170705.        2729351.       10171289.
      2729194.75       10171711.       2729285.5       10172026.
      2729157.25       10173073.       2729252.5       10173202.
       2729913.5       10173464.      2730244.75       10173964.
        2730726.       10175286.      2730677.25       10176110.
       2730835.5       10176411.        2731526.       10177151.
        2731398.       10178661.      2731632.25       10179142.
       2732937.5       10180135.      2733388.25       10180308.
        2733991.       10180977.      2734634.75       10181226.
        2735094.       10181195.      2737129.75       10181780.

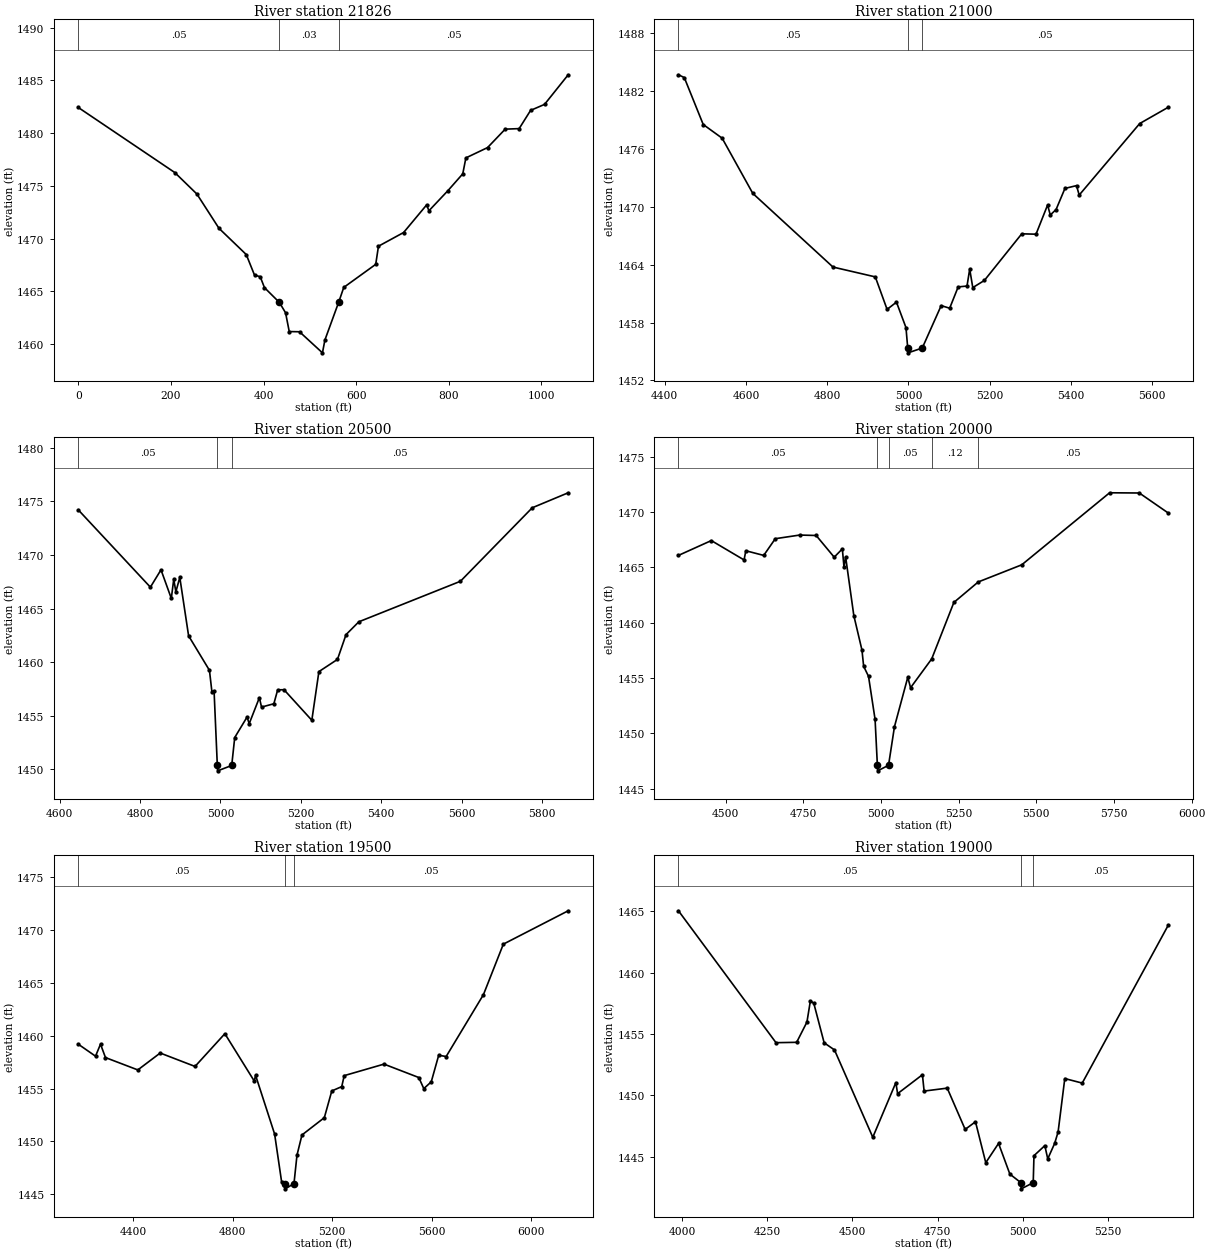
Type RM Length L Ch R = 1 ,21826   ,500,500,500
BEGIN DESCRIPTION:
MARSCHALL BRANCH 43.0
END DESCRIPTION:
XS GIS Cut Line= 3
      2727154.04     10166726.63      2727475.65     10166592.51
      2728138.41     10166339.91
#Sta/Elev= 30
       0 1482.44   208.5 1476.26   256.2 1474.22   303.8 1470.97   362.7 1468.48
   380.6 1466.52   392.8 1466.38     402 1465.34   434.1 1463.94   447.6 1462.95
   455.5 1461.17   477.7 1461.15   527.2 1459.15   532.5 1460.37   562.6    1464
   573.2 1465.36   642.2 1467.55   648.1 1469.27   702.4 1470.57   751.9 1473.18
   757.2 1472.64     798 1474.54   830.1 1476.14   836.8 1477.65   883.6 1478.63
   921.7 1480.38   951.8 1480.43   976.5 1482.16  1006.6 1482.73  1057.7 1485.54
#Mann= 3 , 0 , 0
       0     .05       0   434.1     .03       0   562.6     .05       0
Bank Sta=434.1,562.6
XS Rating Curve= 0 ,0
Exp/Cntr=0.3,0.1

Type RM Length L Ch R = 1 ,21000   ,500,500,500
BEGIN DESCRIPTION:
MARSCHALL BRANCH 42.0
END DESCRIPTION:
XS GIS Cut Line= 3
      2727255.72      10167553.1      2727773.75     10167324.58
      2728255.66     10166903.13
#Sta/Elev= 30
  4433.8 1483.71  4448.2 1483.42  4494.8 1478.55  4541.4 1477.13  4616.9  1471.4
  4814.3 1463.76  4918.5 1462.74  4947.5 1459.37  4970.6 1460.12    4994 1457.48
  4998.3 1455.36  4999.1 1454.86  5034.1 1455.36  5080.7 1459.76  5101.6 1459.49
  5122.5  1461.7  5144.3 1461.79  5150.9 1463.55  5158.5 1461.63    5187 1462.37
  5279.1 1467.21  5314.2 1467.17  5342.7  1470.2  5349.3 1469.16  5363.6 1469.73
  5385.4 1471.92  5413.9 1472.21  5420.5 1471.23  5569.5 1478.65  5640.2 1480.35
#Mann= 3 ,-1 , 0
  4433.8     .05       0  4998.3     .05       0  5034.1     .05       0
Bank Sta=4998.3,5034.1
XS Rating Curve= 0 ,0
Exp/Cntr=0.3,0.1

Type RM Length L Ch R = 1 ,20500   ,500,500,500
BEGIN DESCRIPTION:
MARSCHALL BRANCH 41.0
END DESCRIPTION:
XS GIS Cut Line= 3
       2727405.7      10167903.1      2727741.74     10167791.75
      2728555.91     10167498.13
#Sta/Elev= 30
    4646 1474.21  4825.6 1466.99    4852 1468.61  4877.7 1465.94  4883.7 1467.73
    4889 1466.56  4898.8  1467.9  4920.7 1462.45  4972.6 1459.23  4978.8  1457.2
  4984.1 1457.31  4992.2 1450.35    4993 1449.85    5028 1450.35  5035.5 1452.96
  5066.2 1454.87  5071.5 1454.25  5096.9 1456.68  5102.2  1455.8  5132.9 1456.11
  5142.4 1457.41  5158.2 1457.42  5227.4 1454.57    5245 1459.11  5291.2 1460.25
  5312.5 1462.56  5344.4 1463.76  5597.2 1467.54    5776  1474.4  5865.5  1475.8
#Mann= 3 ,-1 , 0
    4646     .05       0  4992.2     .05       0    5028     .05       0
Bank Sta=4992.2,5028
XS Rating Curve= 0 ,0
Exp/Cntr=0.3,0.1

Type RM Length L Ch R = 1 ,20000   ,500,500,500
BEGIN DESCRIPTION:
MARSCHALL BRANCH 40.0
END DESCRIPTION:
XS GIS Cut Line= 3
      2727375.38     10168426.94      2727993.71     10168220.44
      2728790.29     10167749.86
#Sta/Elev= 30
  4348.1 1466.08  4453.9 1467.42  4559.3 1465.67    4565  1466.5  4622.5 1466.08
  4659.8 1467.59  4738.5 1467.92  4791.4 1467.88  4849.4 1465.92  4875.6 1466.67
    4881 1465.01  4886.2 1465.95  4912.6 1460.64  4938.8 1457.52  4944.2 1456.06
  4959.9 1455.15    4981 1451.26  4988.4 1447.11  4989.2 1446.61  5024.3 1447.11
  5043.4  1450.6  5086.3 1455.07  5095.2 1454.12  5163.3 1456.73  5234.6 1461.83
    5313 1463.68  5453.1 1465.23  5735.9 1471.74  5831.5 1471.72  5925.2  1469.9
#Mann= 5 ,-1 , 0
  4348.1     .05       0  4988.4     .05       0  5024.3     .05       0
  5163.3     .12       0    5313     .05       0
Bank Sta=4988.4,5024.3
XS Rating Curve= 0 ,0
Exp/Cntr=0.3,0.1

Type RM Length L Ch R = 1 ,19500   ,500,500,500
BEGIN DESCRIPTION:
MARSCHALL BRANCH 39.0
END DESCRIPTION:
XS GIS Cut Line= 3
      2727436.12     10168617.91      2728257.39     10168641.23
      2729406.58     10168643.95
#Sta/Elev= 30
  4178.4 1459.21    4248 1458.07    4268 1459.21    4288 1457.94  4418.1 1456.77
  4508.1 1458.37  4648.2  1457.1  4768.2  1460.2  4886.6 1455.71  4891.6 1456.27
  4968.3  1450.7  4996.6 1446.15  5010.3 1446.01  5011.2 1445.51  5046.2 1446.01
  5058.3  1448.7  5078.3 1450.61  5168.3 1452.25  5198.3 1454.78  5238.3 1455.19
  5248.3 1456.23  5408.3 1457.32  5548.3 1456.05  5568.3    1455  5598.3 1455.64
  5628.3 1458.16  5658.3 1458.04  5808.3  1463.9  5888.3 1468.68  6149.2 1471.84
#Mann= 3 ,-1 , 0
  4178.4     .05       0  5010.3     .05       0  5046.2     .05       0
Bank Sta=5010.3,5046.2
XS Rating Curve= 0 ,0
Exp/Cntr=0.3,0.1

Type RM Length L Ch R = 1 ,19000   ,500,500,500
BEGIN DESCRIPTION:
MARSCHALL BRANCH 38.0
END DESCRIPTION:
XS GIS Cut Line= 3
      2727332.02      10168982.5      2728333.18     10169117.31
      2728755.73      10169053.1
#Sta/Elev= 30
  3989.8 1465.03    4276 1454.29  4336.6 1454.32  4366.8 1455.97  4376.9  1457.7
    4387 1457.49  4417.3 1454.28  4447.6  1453.7    4560 1446.59  4627.7 1451.04
  4632.8 1450.14  4705.6 1451.68  4710.6 1450.35  4778.4 1450.59    4831 1447.23
  4861.3 1447.85  4891.5 1444.52    4929 1446.09  4962.2 1443.59  4994.6 1442.89
  4995.4 1442.39  5030.7 1442.89  5032.9 1445.09  5064.8 1445.91  5073.3 1444.83
  5093.6 1446.09  5103.7 1447.02  5123.3 1451.37  5174.5    1451  5427.4 1463.88
#Mann= 3 ,-1 , 0
  3989.8     .05       0  4994.6     .03       0  5030.7     .05       0
Bank Sta=4994.6,5030.7
XS Rating Curve= 0 ,0
Exp/Cntr=0.3,0.1

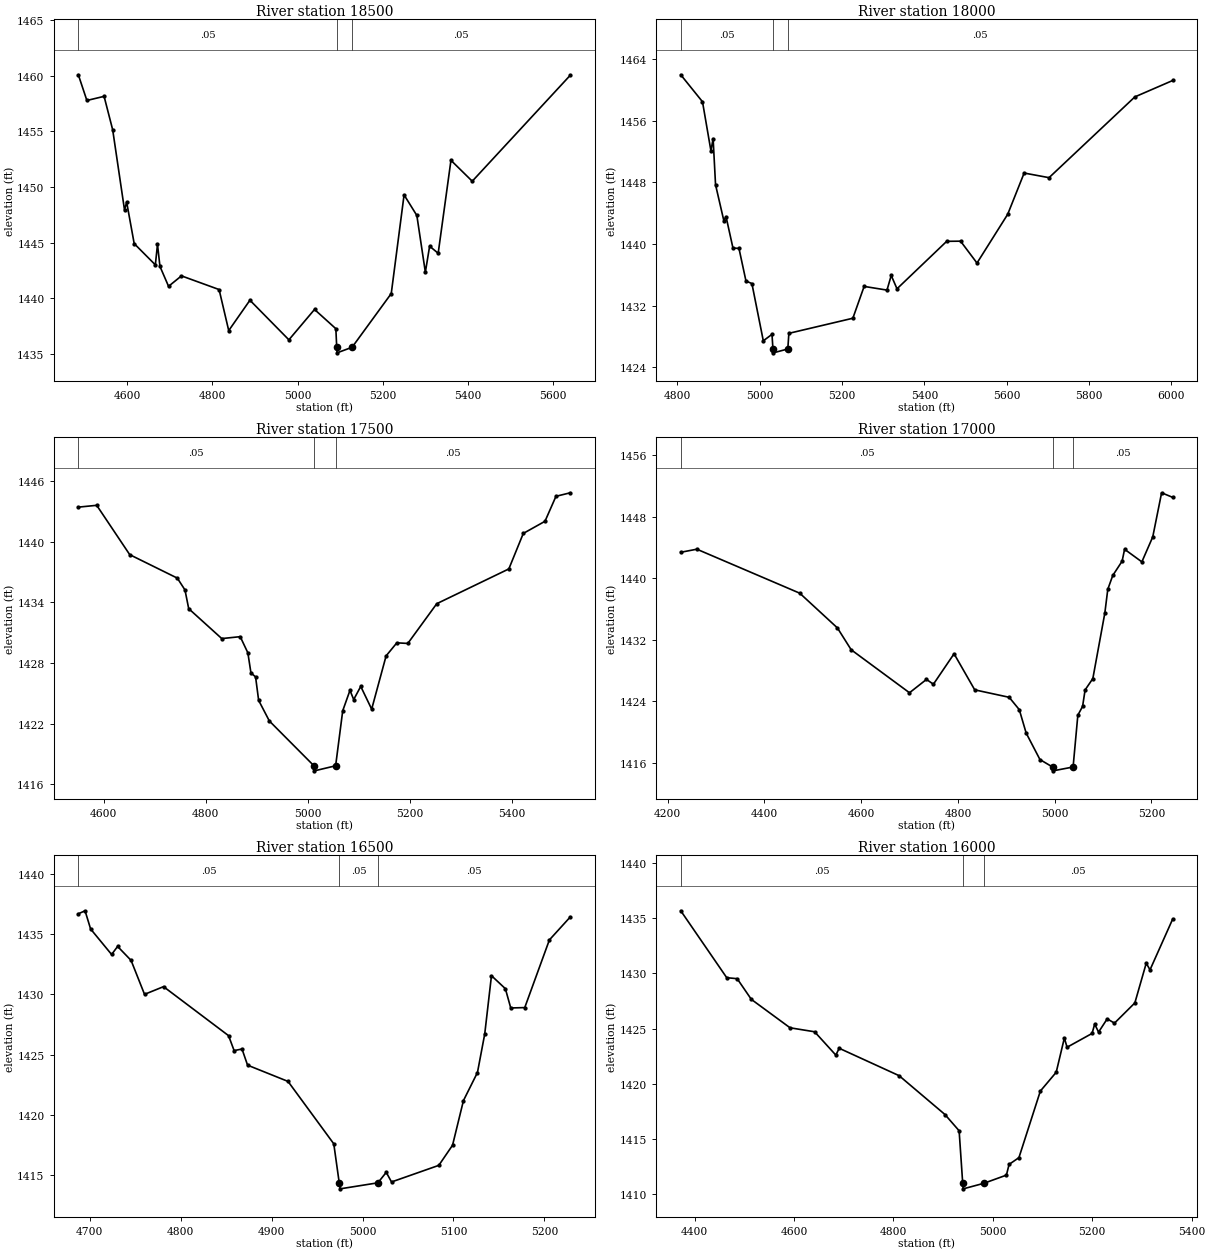
Type RM Length L Ch R = 1 ,18500   ,500,500,500
BEGIN DESCRIPTION:
MARSCHALL BRANCH 37.0
END DESCRIPTION:
XS GIS Cut Line= 3
      2727455.72     10169353.12      2727966.01     10169422.65
      2728605.68     10169453.11
#Sta/Elev= 30
    4485 1460.09  4505.1 1457.78  4545.5 1458.15  4565.7 1455.14  4593.5 1447.93
  4598.5 1448.64  4616.2 1444.91  4665.9    1443  4670.9 1444.84  4676.7 1442.86
  4696.9 1441.07  4727.2 1442.01  4815.6 1440.78  4838.2 1437.09    4888 1439.82
  4979.5 1436.26  5039.7 1438.99  5089.8 1437.26  5091.8 1435.59  5092.6 1435.09
  5127.9 1435.59  5219.9 1440.42    5250 1449.29    5280 1447.44    5300 1442.34
    5310 1444.68  5330.1 1444.04  5360.1  1452.4  5410.1 1450.52  5640.4 1460.05
#Mann= 3 ,-1 , 0
    4485     .05       0  5091.8     .05       0  5127.9     .05       0
Bank Sta=5091.8,5127.9
XS Rating Curve= 0 ,0
Exp/Cntr=0.3,0.1

Type RM Length L Ch R = 1 ,18000   ,500,500,500
BEGIN DESCRIPTION:
MARSCHALL BRANCH 36.0
END DESCRIPTION:
XS GIS Cut Line= 3
      2727505.64      10169703.1       2727687.2     10169764.64
      2728655.71     10169503.11
#Sta/Elev= 30
  4808.3 1461.94  4861.1 1458.44  4881.6 1452.07  4886.9 1453.66  4892.8 1447.67
    4913 1442.99  4918.3 1443.53  4935.1 1439.46  4949.7 1439.41  4966.7 1435.18
  4981.1 1434.85  5008.8 1427.42  5029.9 1428.26  5032.2 1426.36    5033 1425.86
  5068.3 1426.36  5070.9 1428.39  5226.3 1430.35  5253.7 1434.48  5309.2    1434
  5319.5  1435.9  5333.5 1434.17  5454.2 1440.33  5487.9 1440.35  5527.8 1437.51
  5602.4 1443.84  5642.3 1449.19  5702.8 1448.59  5911.2 1459.07  6003.2  1461.2
#Mann= 3 ,-1 , 0
  4808.3     .05       0  5032.2     .05       0  5068.3     .05       0
Bank Sta=5032.2,5068.3
XS Rating Curve= 0 ,0
Exp/Cntr=0.3,0.1

Type RM Length L Ch R = 1 ,17500   ,500,500,500
BEGIN DESCRIPTION:
MARSCHALL BRANCH 35.0
END DESCRIPTION:
XS GIS Cut Line= 3
      2727605.69     10170353.11      2727979.92     10170104.11
      2728355.69     10169753.11
#Sta/Elev= 30
  4550.5 1443.43  4586.5 1443.61  4651.2 1438.73  4744.4 1436.41  4759.4 1435.24
  4766.7 1433.39  4831.5 1430.43  4867.6 1430.62  4882.6 1429.02  4888.6 1427.04
  4897.7 1426.64  4903.7 1424.32  4924.7 1422.28    5012 1417.85    5013 1417.35
  5054.5 1417.85  5068.4 1423.29  5082.6 1425.31  5089.9  1424.4  5103.7  1425.7
  5125.1 1423.45  5153.4 1428.72  5174.4 1430.01  5195.9 1429.95  5252.6 1433.88
  5393.8 1437.32  5422.1 1440.83  5464.6 1442.03  5486.1  1444.5  5514.2 1444.85
#Mann= 3 ,-1 , 0
  4550.5     .05       0    5012     .05       0  5054.5     .05       0
Bank Sta=5012,5054.5
XS Rating Curve= 0 ,0
Exp/Cntr=0.3,0.1

Type RM Length L Ch R = 1 ,17000   ,500,500,500
BEGIN DESCRIPTION:
MARSCHALL BRANCH 34.0
END DESCRIPTION:
XS GIS Cut Line= 3
      2727960.63     10170745.26      2728469.38     10170163.54
      2728705.67     10170103.11
#Sta/Elev= 30
  4227.2 1443.39  4260.5 1443.79  4473.1 1438.06  4550.9 1433.54  4579.4 1430.69
  4699.9 1425.09    4735 1426.83  4749.3  1426.2    4792 1430.17  4834.7 1425.47
  4905.9  1424.5  4926.8 1422.89    4941 1419.84  4969.5 1416.39  4995.5 1415.42
  4996.5 1414.92    5038 1415.42  5047.8 1422.17  5057.6 1423.31  5062.8 1425.46
  5078.8 1426.94  5103.6 1435.48  5109.7 1438.57    5120 1440.37  5139.3 1442.23
  5144.4 1443.78  5180.1 1442.14  5202.6 1445.39  5220.9 1451.14  5243.9 1450.54
#Mann= 3 ,-1 , 0
  4227.2     .05       0  4995.5     .05       0    5038     .05       0
Bank Sta=4995.5,5038
XS Rating Curve= 0 ,0
Exp/Cntr=0.3,0.1

Type RM Length L Ch R = 1 ,16500   ,500,500,500
BEGIN DESCRIPTION:
MARSCHALL BRANCH 33.0
END DESCRIPTION:
XS GIS Cut Line= 3
      2728605.68     10170803.12      2728785.05     10170547.22
      2728905.66     10170353.15
#Sta/Elev= 30
  4687.5  1436.7  4694.9 1436.95    4701 1435.44  4724.1 1433.32  4730.7 1433.99
  4745.5 1432.83  4760.3 1430.01  4781.2 1430.65  4852.7 1426.58  4858.8 1425.34
  4867.5 1425.47  4873.6 1424.13  4918.1 1422.78  4968.4  1417.6  4974.4 1414.36
  4975.4 1413.86  5016.9 1414.36  5026.1 1415.23  5031.9 1414.43  5083.9 1415.81
    5099 1417.48    5111 1421.19  5126.4 1423.52  5134.4 1426.72  5141.8 1431.56
  5157.1 1430.48    5163 1428.88  5178.4 1428.91  5205.5 1434.53  5228.5 1436.44
#Mann= 3 ,-1 , 0
  4687.5     .05       0  4974.4     .05       0  5016.9     .05       0
Bank Sta=4974.4,5016.9
XS Rating Curve= 0 ,0
Exp/Cntr=0.3,0.1

Type RM Length L Ch R = 1 ,16000   ,500,500,500
BEGIN DESCRIPTION:
MARSCHALL BRANCH 32.0
END DESCRIPTION:
XS GIS Cut Line= 3
      2728655.71     10171303.09      2729130.95     10170892.72
      2729255.69     10170553.11
#Sta/Elev= 30
  4372.1 1435.65  4464.6  1429.6  4485.6 1429.51  4514.1 1427.64    4592 1425.07
  4641.4 1424.71  4684.1  1422.6  4690.8 1423.22  4811.4 1420.74  4903.6 1417.23
  4932.1 1415.76  4939.3 1411.01  4940.3 1410.51  4981.8 1411.01  5027.2 1411.75
  5032.6 1412.72  5052.4 1413.33  5095.5 1419.35  5127.4 1421.05  5143.8 1424.15
  5149.2 1423.31  5199.5 1424.56  5204.8  1425.4  5212.6 1424.68    5230 1425.88
  5244.6 1425.49  5285.6 1427.32  5308.5 1430.91  5316.1 1430.31  5361.8 1434.91
#Mann= 3 ,-1 , 0
  4372.1     .05       0  4939.3     .03       0  4981.8     .05       0
Bank Sta=4939.3,4981.8
XS Rating Curve= 0 ,0
Exp/Cntr=0.3,0.1

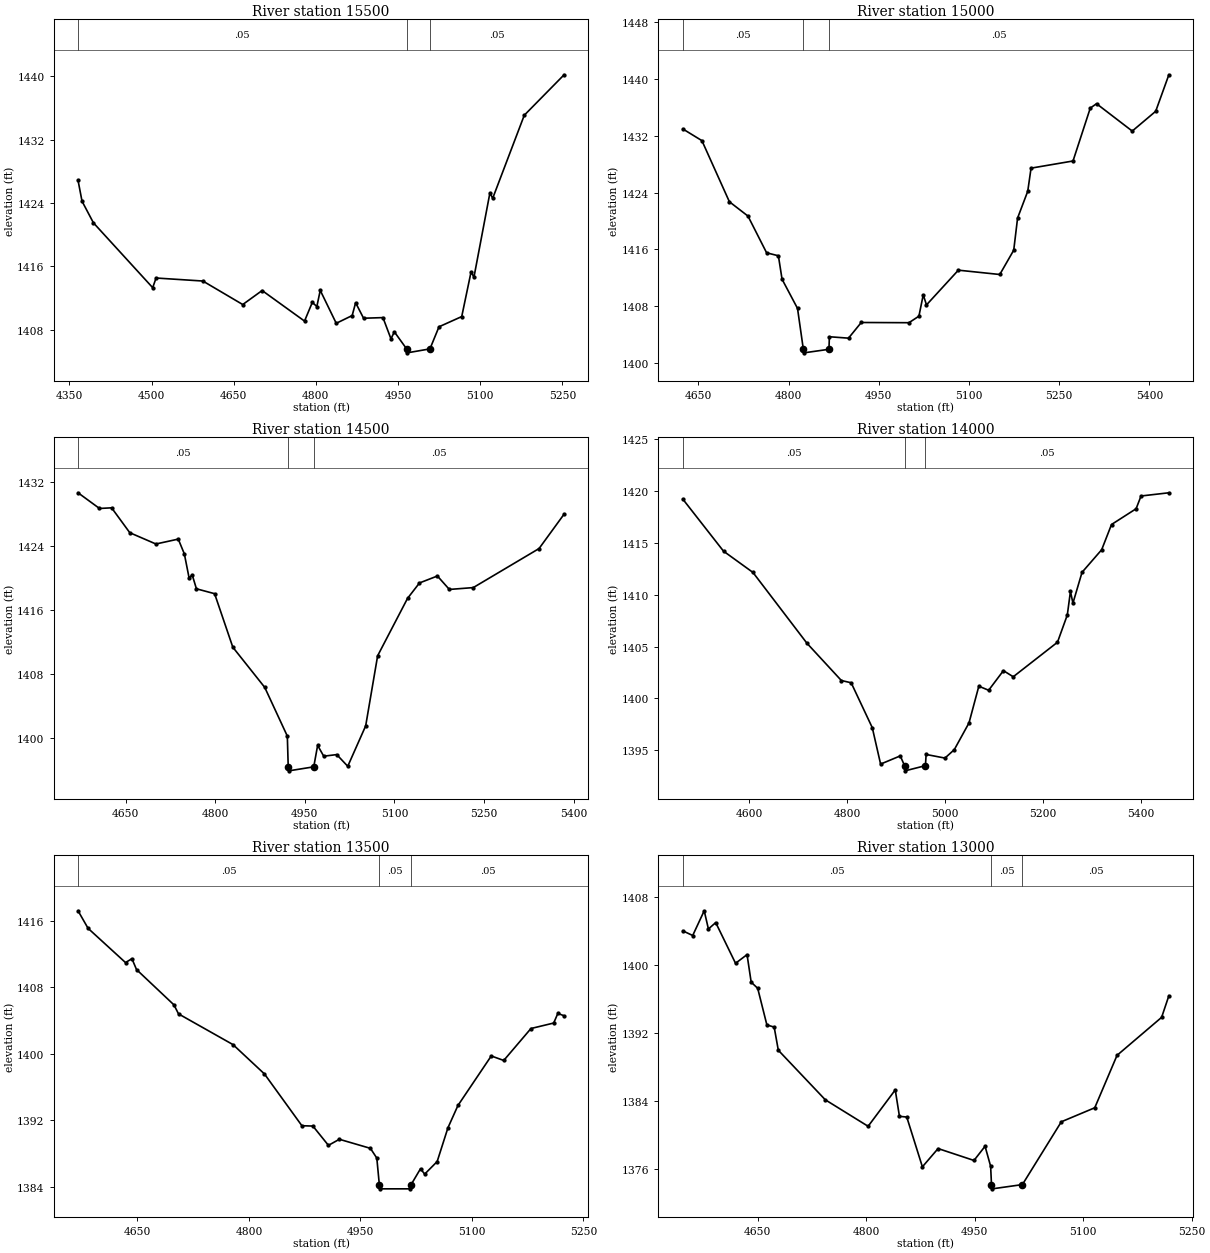
Type RM Length L Ch R = 1 ,15500   ,500,500,500
BEGIN DESCRIPTION:
MARSCHALL BRANCH 31.0
END DESCRIPTION:
XS GIS Cut Line= 3
      2728855.71      10171703.1      2729361.75     10171320.83
      2729605.73      10171253.1
#Sta/Elev= 30
  4365.8 1426.88  4373.1 1424.24  4393.9 1421.51  4502.1 1413.32  4508.3 1414.54
  4593.7 1414.16  4666.5 1411.19  4701.9 1412.96  4779.3  1409.1  4793.5 1411.46
  4801.8 1410.94    4808 1412.98  4837.2 1408.82  4866.3  1409.8  4872.6 1411.42
  4887.1 1409.46  4922.5 1409.54  4937.1 1406.86  4943.3 1407.74  4965.7 1405.59
  4966.7 1405.09  5008.3 1405.59  5024.8 1408.38  5066.3 1409.67  5083.4 1415.33
  5088.6 1414.64  5117.7 1425.27  5122.9 1424.62  5180.5  1435.1  5253.2 1440.21
#Mann= 3 ,-1 , 0
  4365.8     .05       0  4965.7     .05       0  5008.3     .05       0
Bank Sta=4965.7,5008.3
XS Rating Curve= 0 ,0
Exp/Cntr=0.3,0.1

Type RM Length L Ch R = 1 ,15000   ,500,500,500
BEGIN DESCRIPTION:
MARSCHALL BRANCH 30.0
END DESCRIPTION:
XS GIS Cut Line= 3
       2728855.7     10171903.11      2729210.54     10171778.46
      2729605.68     10171603.11
#Sta/Elev= 30
  4623.9 1432.98  4655.7 1431.33  4701.4 1422.71  4732.3 1420.69  4763.3 1415.51
  4782.9 1415.09    4789 1411.78  4814.7 1407.67  4824.4  1401.9  4825.4  1401.4
    4867  1401.9  4867.7 1403.67  4899.5 1403.47  4920.7 1405.68    5000 1405.65
  5016.6 1406.57  5023.8 1409.58  5029.2 1408.16  5082.2 1413.06  5151.1 1412.45
  5174.3 1415.88  5180.7 1420.41  5197.6 1424.19  5203.1 1427.45  5272.9 1428.46
  5301.6 1435.92    5312 1436.54  5371.4 1432.68  5410.4 1435.47  5432.3 1440.62
#Mann= 3 ,-1 , 0
  4623.9     .05       0  4824.4     .05       0    4867     .05       0
Bank Sta=4824.4,4867
XS Rating Curve= 0 ,0
Exp/Cntr=0.3,0.1

Type RM Length L Ch R = 1 ,14500   ,500,500,500
BEGIN DESCRIPTION:
MARSCHALL BRANCH 29.0
END DESCRIPTION:
XS GIS Cut Line= 3
      2728790.27     10172176.93      2729213.88     10172247.84
      2729597.61     10172255.06
#Sta/Elev= 30
  4570.5 1430.65  4606.4 1428.69  4626.7 1428.77  4657.1 1425.66  4700.8 1424.25
  4738.2 1424.86  4748.4 1423.01  4756.4 1419.98  4761.5  1420.4  4768.6 1418.65
    4799 1418.04  4829.5 1411.35  4882.9 1406.33  4920.7 1400.24  4922.2  1396.4
  4923.2  1395.9  4964.9  1396.4  4971.4 1399.08  4981.6 1397.73  5003.4 1397.93
  5021.8 1396.47  5051.8 1401.52  5071.8 1410.28  5121.8 1417.45  5141.8 1419.38
  5171.8 1420.25  5191.8 1418.57  5231.8  1418.8  5341.9 1423.68  5383.8 1427.98
#Mann= 3 ,-1 , 0
  4570.5     .05       0  4922.2     .05       0  4964.9     .05       0
Bank Sta=4922.2,4964.9
XS Rating Curve= 0 ,0
Exp/Cntr=0.3,0.1

Type RM Length L Ch R = 1 ,14000   ,500,500,500
BEGIN DESCRIPTION:
MARSCHALL BRANCH 28.0
END DESCRIPTION:
XS GIS Cut Line= 3
      2728642.74     10172793.26      2729176.71     10172744.39
      2729632.33     10172697.77
#Sta/Elev= 30
  4463.8 1419.22  4547.1  1414.2  4607.3 1412.15  4717.8 1405.32  4788.1 1401.73
  4808.2 1401.51  4851.4 1397.18  4868.4 1393.67  4908.6 1394.46  4917.4 1393.52
  4918.4 1393.02  4960.1 1393.52  4961.5  1394.6    5000 1394.25  5019.1 1395.06
  5049.2 1397.64  5069.3 1401.18  5089.4 1400.79  5119.6 1402.68  5139.7 1402.09
  5230.2 1405.42  5250.3 1408.05  5256.7 1410.32  5261.8 1409.19  5280.4 1412.16
  5320.6 1414.34  5340.7 1416.77    5391 1418.29  5401.1 1419.52    5458 1419.83
#Mann= 3 ,-1 , 0
  4463.8     .05       0  4917.4     .05       0  4960.1     .05       0
Bank Sta=4917.4,4960.1
XS Rating Curve= 0 ,0
Exp/Cntr=0.3,0.1

Type RM Length L Ch R = 1 ,13500   ,500,500,500
BEGIN DESCRIPTION:
MARSCHALL BRANCH 27.0
END DESCRIPTION:
XS GIS Cut Line= 3
      2728905.72     10173453.09      2729256.04     10173203.74
      2729355.68     10173003.12
#Sta/Elev= 30
    4570 1417.18  4583.5 1415.07  4633.9 1410.95  4642.5 1411.42  4648.7 1410.11
  4699.1 1405.86  4705.2 1404.78  4778.6 1401.08  4820.8 1397.56  4871.2 1391.33
    4886 1391.29  4906.9 1388.97  4921.6  1389.7  4963.4 1388.61    4972 1387.44
  4975.4 1384.24  4976.4 1383.74  5017.1 1383.74  5018.1 1384.24  5030.8 1386.16
  5036.4 1385.51  5053.2 1387.02  5067.7 1391.08  5081.2 1393.77    5126 1399.72
  5142.8 1399.18  5179.4 1403.02    5210 1403.68  5215.6 1404.84    5224 1404.55
#Mann= 3 ,-1 , 0
    4570     .05       0  4975.4     .05       0  5018.1     .05       0
Bank Sta=4975.4,5018.1
XS Rating Curve= 0 ,0
Exp/Cntr=0.3,0.1

Type RM Length L Ch R = 1 ,13000   ,500,500,500
BEGIN DESCRIPTION:
MARSCHALL BRANCH 26.0
END DESCRIPTION:
XS GIS Cut Line= 3
      2729505.66     10173753.15      2729729.22     10173358.81
       2729655.7     10173153.15
#Sta/Elev= 30
  4546.7 1404.06  4560.4 1403.51  4576.3 1406.42  4582.1 1404.28  4592.2 1405.03
  4619.6 1400.24  4635.5 1401.26  4641.2 1398.02  4650.2  1397.3  4662.9 1392.99
    4673 1392.73  4678.7 1390.01  4743.6 1384.18  4802.8 1381.06  4840.3 1385.34
  4846.1 1382.23  4856.2 1382.15  4877.8 1376.29  4899.5 1378.44  4949.1 1377.04
  4964.4 1378.71  4972.1 1376.36  4973.3  1374.2  4974.3  1373.7    5016  1374.2
  5069.8 1381.59    5116 1383.24  5146.8 1389.41  5208.4 1393.88  5218.4 1396.42
#Mann= 3 ,-1 , 0
  4546.7     .05       0  4973.3     .05       0    5016     .05       0
Bank Sta=4973.3,5016
XS Rating Curve= 0 ,0
Exp/Cntr=0.3,0.1

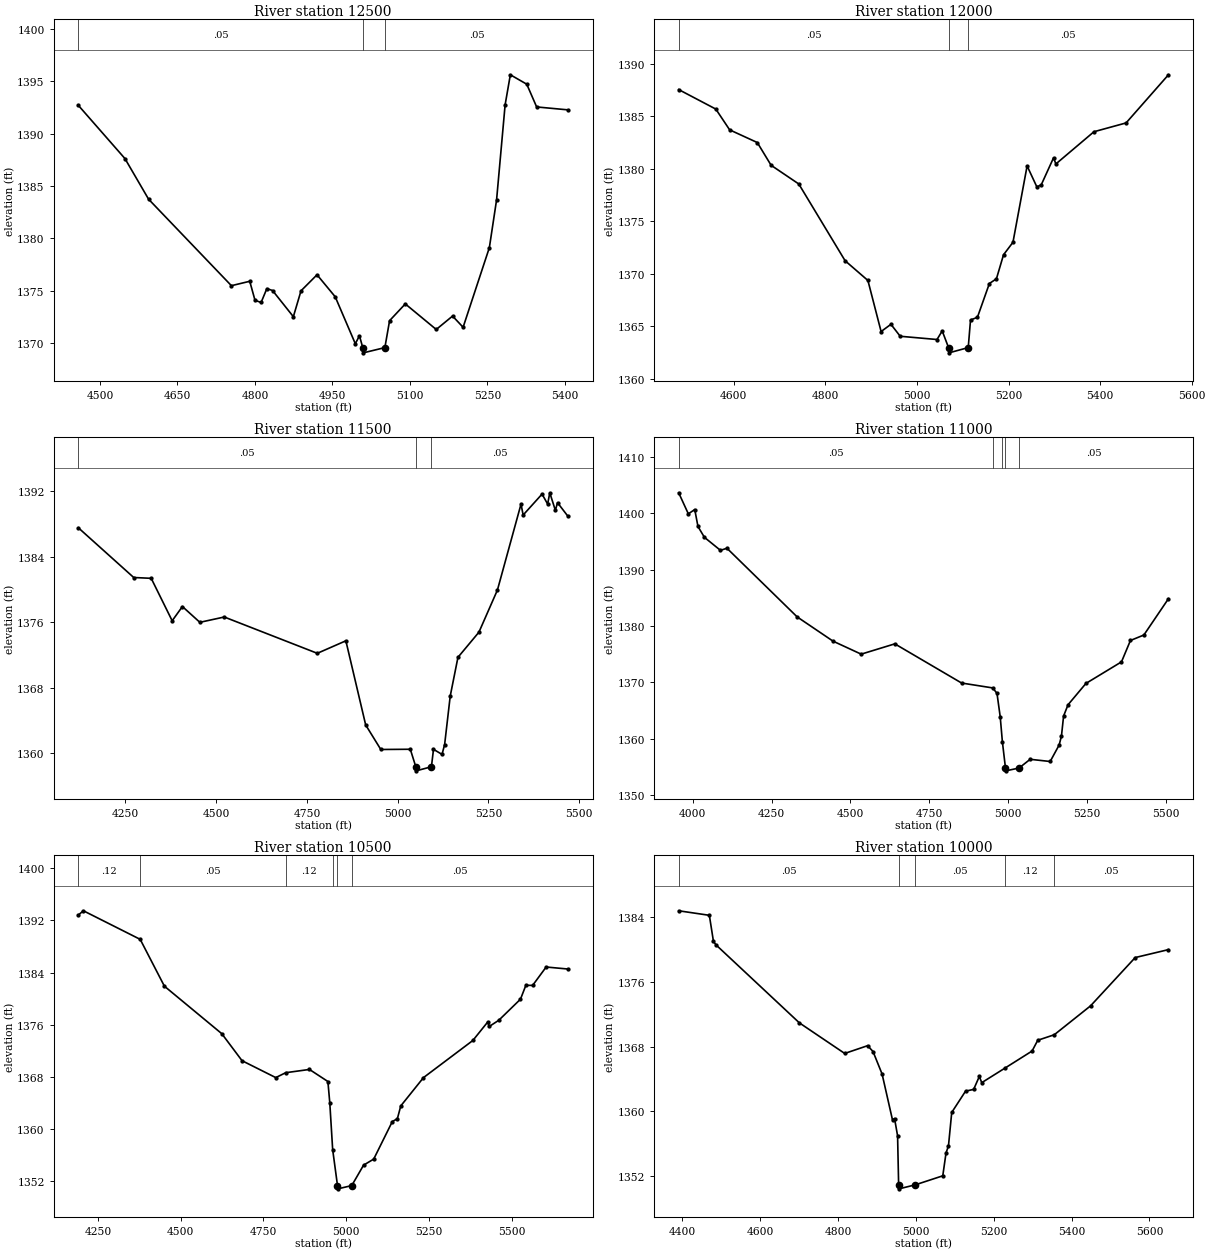
Type RM Length L Ch R = 1 ,12500   ,500,500,500
BEGIN DESCRIPTION:
MARSCHALL BRANCH 25.0
END DESCRIPTION:
XS GIS Cut Line= 3
      2729614.97     10173904.36      2730106.11     10173675.84
      2730505.64     10173603.12
#Sta/Elev= 30
  4458.3  1392.7  4548.5 1387.62  4594.3 1383.74  4754.5 1375.49    4790 1375.91
  4800.2 1374.09    4812 1373.89  4823.1 1375.21  4834.1 1375.03  4874.4 1372.53
  4889.2    1375  4920.2 1376.53  4955.4 1374.43  4994.3 1369.95  5002.3 1370.71
  5008.7 1369.58  5009.7 1369.08  5051.5 1369.58  5060.6 1372.15    5091 1373.75
  5150.9 1371.31  5182.5 1372.59  5202.9 1371.52  5253.7 1379.12  5267.7 1383.69
  5284.2 1392.75  5294.3 1395.62  5326.1 1394.72  5345.2 1392.55  5406.1 1392.27
#Mann= 3 ,-1 , 0
  4458.3     .05       0  5008.7     .05       0  5051.5     .05       0
Bank Sta=5008.7,5051.5
XS Rating Curve= 0 ,0
Exp/Cntr=0.3,0.1

Type RM Length L Ch R = 1 ,12000   ,500,500,500
BEGIN DESCRIPTION:
MARSCHALL BRANCH 24.0
END DESCRIPTION:
XS GIS Cut Line= 3
      2729745.13     10174199.51      2730262.06     10174139.51
      2730795.52     10174008.53
#Sta/Elev= 30
  4479.6 1387.56  4560.7  1385.7  4590.9 1383.72  4651.3 1382.51  4681.5 1380.34
  4741.9 1378.56  4843.1 1371.24  4892.9 1369.36  4921.7 1364.49  4943.2 1365.18
  4963.4 1364.04  5043.8 1363.73  5055.2 1364.55    5069 1362.96    5070 1362.46
    5112 1362.96    5117 1365.59  5132.1 1365.85  5158.2 1369.07  5173.6 1369.52
  5189.1 1371.81  5209.7    1373  5240.6 1380.28  5261.9 1378.28  5271.5 1378.48
  5298.3 1381.05  5303.5 1380.47  5386.6 1383.54  5456.8 1384.38  5549.3 1388.97
#Mann= 3 ,-1 , 0
  4479.6     .05       0    5069     .03       0    5112     .05       0
Bank Sta=5069,5112
XS Rating Curve= 0 ,0
Exp/Cntr=0.3,0.1

Type RM Length L Ch R = 1 ,11500   ,500,500,500
BEGIN DESCRIPTION:
MARSCHALL BRANCH 23.0
END DESCRIPTION:
XS GIS Cut Line= 3
       2729623.6     10174772.43      2730481.48     10174576.82
      2730881.48     10174330.23
#Sta/Elev= 30
  4120.1 1387.55  4272.7 1381.47  4320.9 1381.37  4378.7 1376.18  4406.9 1377.92
    4455 1375.99  4522.3 1376.64  4778.7  1372.2  4857.4 1373.73    4912 1363.44
  4953.7 1360.44    5035 1360.47  5050.1 1358.33  5051.1 1357.83  5093.2 1358.33
  5098.9 1360.46  5122.4 1359.84  5129.6 1361.05    5145 1366.97  5166.3 1371.71
  5224.2 1374.79  5275.1 1379.94  5340.1 1390.44    5346 1389.11  5398.1 1391.67
  5413.5 1390.45  5419.4 1391.83  5434.8 1389.68  5440.7 1390.62  5469.9 1388.93
#Mann= 3 ,-1 , 0
  4120.1     .05       0  5050.1     .03       0  5093.2     .05       0
Bank Sta=5050.1,5093.2
XS Rating Curve= 0 ,0
Exp/Cntr=0.3,0.1

Type RM Length L Ch R = 1 ,11000   ,500,500,500
BEGIN DESCRIPTION:
MARSCHALL BRANCH 22.0
END DESCRIPTION:
XS GIS Cut Line= 3
      2729605.65     10175253.12      2730629.84     10175046.62
      2731005.71     10174703.09
#Sta/Elev= 30
  3955.2 1403.68  3985.8 1399.94  4006.2  1400.7  4016.4 1397.69  4036.8 1395.77
  4087.8 1393.45  4108.3 1393.83  4331.1 1381.63  4444.9 1377.32  4534.3 1375.01
    4641 1376.84  4852.9 1369.88  4951.7 1369.01  4965.2 1368.04  4975.4 1363.89
  4982.3 1359.44  4992.1 1354.78  4993.1 1354.28  5035.2 1354.78  5070.4 1356.33
  5133.9 1355.94  5162.3 1358.86  5169.7 1360.45  5176.5 1364.02  5190.6 1366.02
  5247.4 1369.81  5360.2 1373.64  5388.6 1377.44  5431.2 1378.41  5509.2 1384.86
#Mann= 5 ,-1 , 0
  3955.2     .05       0  4951.7     .12       0  4982.3     .05       0
  4992.1     .05       0  5035.2     .05       0
Bank Sta=4992.1,5035.2
XS Rating Curve= 0 ,0
Exp/Cntr=0.3,0.1

Type RM Length L Ch R = 1 ,10500   ,500,500,500
BEGIN DESCRIPTION:
MARSCHALL BRANCH 21.0
END DESCRIPTION:
XS GIS Cut Line= 3
      2729880.68     10175678.11      2730674.19     10175516.99
      2731330.66     10175378.12
#Sta/Elev= 30
  4190.3 1392.83  4205.6 1393.48  4377.3  1389.1  4450.5 1381.92    4624 1374.64
  4685.2  1370.5  4787.2 1367.91  4817.2 1368.66    4889 1369.16  4944.8 1367.31
  4950.5 1364.03  4959.2 1356.87  4973.8 1351.36  4974.8 1350.86  5016.9 1351.36
  5052.6 1354.49  5083.3 1355.42  5139.5 1361.17  5154.8 1361.61  5165.1 1363.57
  5233.8 1367.91    5383  1373.6  5427.6 1376.41  5432.7 1375.75  5461.5  1376.7
    5527 1379.93  5543.3 1382.06  5563.7 1382.04  5604.6 1384.86    5671 1384.55
#Mann= 6 ,-1 , 0
  4190.3     .12       0  4377.3     .05       0  4817.2     .12       0
  4959.2     .05       0  4973.8     .05       0  5016.9     .05       0
Bank Sta=4973.8,5016.9
XS Rating Curve= 0 ,0
Exp/Cntr=0.3,0.1

Type RM Length L Ch R = 1 ,10000   ,500,500,500
BEGIN DESCRIPTION:
MARSCHALL BRANCH 20.0
END DESCRIPTION:
XS GIS Cut Line= 3
      2730080.71     10175828.12       2730660.5     10176015.77
      2731180.65     10175628.14
#Sta/Elev= 30
  4390.6 1384.78  4469.4 1384.22  4479.9    1381  4486.6 1380.56  4700.6 1370.93
  4817.1 1367.15  4875.9 1368.11  4889.8 1367.39  4913.1 1364.61  4939.9 1358.92
  4945.1 1359.11  4952.9 1356.98  4955.6 1350.92  4956.6 1350.42  4998.7 1350.92
    5069 1352.03  5077.4 1354.87  5083.6 1355.71    5092 1359.86  5127.5 1362.49
  5148.3 1362.71  5162.9 1364.31  5169.1 1363.54  5228.1 1365.32  5298.4 1367.45
    5313 1368.78  5355.4 1369.46  5448.6 1373.03  5563.3    1379  5648.7 1379.98
#Mann= 5 ,-1 , 0
  4390.6     .05       0  4955.6     .05       0  4998.7     .05       0
  5228.1     .12       0  5355.4     .05       0
Bank Sta=4955.6,4998.7
XS Rating Curve= 0 ,0
Exp/Cntr=0.3,0.1

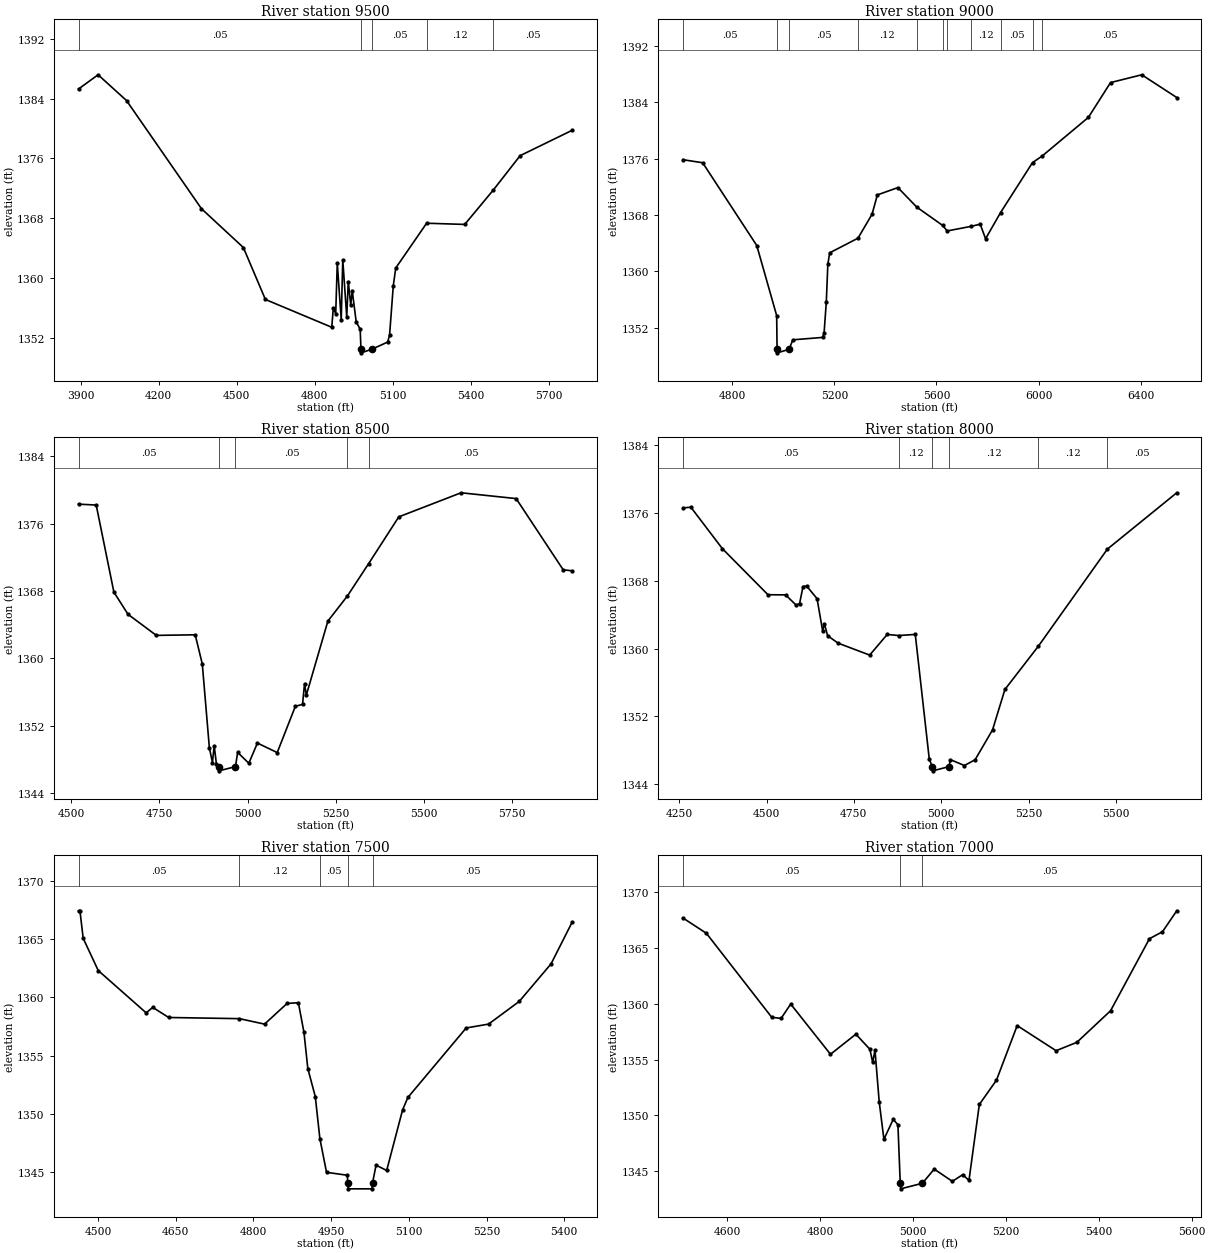
Type RM Length L Ch R = 1 ,9500    ,500,500,500
BEGIN DESCRIPTION:
MARSCHALL BRANCH 19.0
END DESCRIPTION:
XS GIS Cut Line= 3
      2729939.83     10177049.98      2730876.24     10176457.14
      2731180.67     10175728.15
#Sta/Elev= 30
  3891.7 1385.29  3966.9 1387.19  4076.2 1383.74  4364.4 1369.27  4525.4 1364.08
  4610.1 1357.13  4865.3 1353.41  4871.2 1355.97  4880.5 1355.24  4886.5 1361.99
  4901.7 1354.43  4907.6 1362.45  4922.9 1354.79  4928.8 1359.53  4938.2 1356.39
  4944.1 1358.27  4959.4 1354.11  4974.6 1353.15  4977.5 1350.49  4978.5 1349.99
  5020.7 1350.49  5080.2 1351.43  5087.5 1352.34  5101.9 1358.98  5111.3 1361.34
    5230 1367.33  5376.5 1367.17    5485 1371.71  5589.6 1376.37    5790 1379.77
#Mann= 5 ,-1 , 0
  3891.7     .05       0  4977.5     .05       0  5020.7     .05       0
    5230     .12       0    5485     .05       0
Bank Sta=4977.5,5020.7
XS Rating Curve= 0 ,0
Exp/Cntr=0.3,0.1

Type RM Length L Ch R = 1 ,9000    ,500,500,500
BEGIN DESCRIPTION:
MARSCHALL BRANCH 18.0
END DESCRIPTION:
XS GIS Cut Line= 3
      2730969.16     10177055.38      2731252.44     10176782.55
      2732127.35     10175513.51
#Sta/Elev= 30
  4606.7 1375.86  4683.7 1375.43  4895.7 1363.67  4973.7 1353.71  4975.3 1348.92
  4976.3 1348.42  5022.3 1348.92    5037 1350.27  5153.3 1350.61  5159.4 1351.18
  5168.2 1355.66  5174.3 1361.05  5181.5 1362.63  5292.3 1364.71  5347.4 1368.11
  5368.3 1370.86  5448.7  1371.9  5522.6 1369.13  5623.8 1366.53  5642.1 1365.74
  5735.3 1366.39  5771.3  1366.7  5792.3 1364.63  5851.2 1368.36  5976.2 1375.45
  6013.5 1376.37  6195.3 1381.88  6281.9 1386.82  6404.3 1387.93  6541.4  1384.7
#Mann= 11 ,-1 , 0
  4606.7     .05       0  4975.3     .05       0  5022.3     .05       0
  5292.3     .12       0  5522.6     .05       0  5623.8     .12       0
  5642.1     .05       0  5735.3     .12       0  5851.2     .05       0
  5976.2     .12       0  6013.5     .05       0
Bank Sta=4975.3,5022.3
XS Rating Curve= 0 ,0
Exp/Cntr=0.3,0.1

Type RM Length L Ch R = 1 ,8500    ,500,500,500
BEGIN DESCRIPTION:
MARSCHALL BRANCH 17.0
END DESCRIPTION:
XS GIS Cut Line= 3
      2731055.65     10177153.11      2731533.83     10177184.38
      2732430.72      10176978.1
#Sta/Elev= 30
  4520.8  1378.3  4570.9 1378.19    4621 1367.85  4661.1 1365.21  4741.3 1362.71
  4851.5 1362.78  4871.6 1359.31  4891.6 1349.37  4900.3 1347.61  4905.3 1349.61
  4911.7  1347.4  4917.9 1347.12  4918.9 1346.62  4965.6 1347.12  4971.8 1348.81
  5003.5 1347.52  5027.8 1349.92    5084 1348.79  5135.3 1354.28  5155.8 1354.52
  5161.4 1356.98  5166.5 1355.62  5227.6 1364.41  5282.9 1367.39    5343 1371.23
  5428.6 1376.79  5605.1 1379.65  5761.2 1378.96  5894.6  1370.5  5920.3 1370.38
#Mann= 5 ,-1 , 0
  4520.8     .05       0  4917.9     .05       0  4965.6     .05       0
  5282.9     .12       0    5343     .05       0
Bank Sta=4917.9,4965.6
XS Rating Curve= 0 ,0
Exp/Cntr=0.3,0.1

Type RM Length L Ch R = 1 ,8000    ,500,500,500
BEGIN DESCRIPTION:
MARSCHALL BRANCH 16.0
END DESCRIPTION:
XS GIS Cut Line= 3
      2730743.42     10177602.28      2731479.56     10177668.36
       2732149.7      10177593.6
#Sta/Elev= 30
  4260.9 1376.61  4283.3  1376.7  4373.6  1371.8  4504.1 1366.36  4554.6 1366.34
  4584.5 1365.14  4594.5  1365.3  4604.5 1367.33  4614.6  1367.4  4644.7 1365.89
  4660.7 1362.07  4665.7 1362.94  4674.8 1361.52  4704.9 1360.64  4795.3 1359.23
  4845.5 1361.67  4878.1 1361.54  4925.8 1361.67    4966  1346.9  4974.8 1346.06
  4975.8 1345.56  5022.5 1346.06  5026.3 1346.88  5066.5 1346.19  5097.1 1346.87
    5147  1350.4  5182.4 1355.17  5277.8 1360.26  5475.8 1371.75  5674.3  1378.4
#Mann= 6 ,-1 , 0
  4260.9     .05       0  4878.1     .12       0  4974.8     .03       0
  5022.5     .12       0  5277.8     .12       0  5475.8     .05       0
Bank Sta=4974.8,5022.5
XS Rating Curve= 0 ,0
Exp/Cntr=0.3,0.1

Type RM Length L Ch R = 1 ,7500    ,500,500,500
BEGIN DESCRIPTION:
MARSCHALL BRANCH 15.0
END DESCRIPTION:
XS GIS Cut Line= 3
      2730955.73     10177953.13      2731449.81     10178164.76
       2731855.7     10178253.12
#Sta/Elev= 30
  4462.5 1367.45  4465.2 1367.45  4471.5 1365.08  4500.5 1362.31    4593 1358.67
  4605.7 1359.14  4636.5 1358.27  4773.1 1358.17  4821.5  1357.7    4865 1359.48
  4886.8 1359.54  4897.6 1356.98    4905 1353.88  4919.4 1351.47  4928.3 1347.85
  4941.1 1344.95  4981.2  1344.7  4982.2 1344.03  4983.2 1343.53  5028.9 1343.53
  5029.9 1344.03  5036.7 1345.57  5057.2 1345.11  5087.9 1350.32  5098.1 1351.39
  5210.7 1357.37  5253.8  1357.7    5313 1359.65  5374.4 1362.88  5415.4 1366.49
#Mann= 5 ,-1 , 0
  4462.5     .05       0  4773.1     .12       0  4928.3     .05       0
  4982.2     .03       0  5029.9     .05       0
Bank Sta=4982.2,5029.9
XS Rating Curve= 0 ,0
Exp/Cntr=0.3,0.1

Type RM Length L Ch R = 1 ,7000    ,500,500,500
BEGIN DESCRIPTION:
MARSCHALL BRANCH 14.0
END DESCRIPTION:
XS GIS Cut Line= 3
       2730905.7     10178603.11        2731398.     10178657.57
       2731905.7      10178403.1
#Sta/Elev= 30
  4504.7 1367.68  4555.1 1366.31  4695.8 1358.78    4716 1358.69  4736.6 1359.97
  4822.3 1355.47  4876.9 1357.27  4907.1 1355.92  4913.1 1354.75  4918.1 1355.84
  4927.2  1351.2  4937.3 1347.85  4957.4 1349.64  4967.5 1349.15  4972.5 1343.91
  4973.5 1343.41  5020.2 1343.91  5045.6 1345.18  5084.7 1344.08    5107 1344.68
  5120.5 1344.17  5142.8 1350.97  5179.7 1353.15  5224.3 1358.04  5308.1 1355.79
  5352.8 1356.54  5425.4 1359.37  5509.2 1365.83  5537.2 1366.45  5567.9 1368.33
#Mann= 3 ,-1 , 0
  4504.7     .05       0  4972.5     .03       0  5020.2     .05       0
Bank Sta=4972.5,5020.2
XS Rating Curve= 0 ,0
Exp/Cntr=0.3,0.1