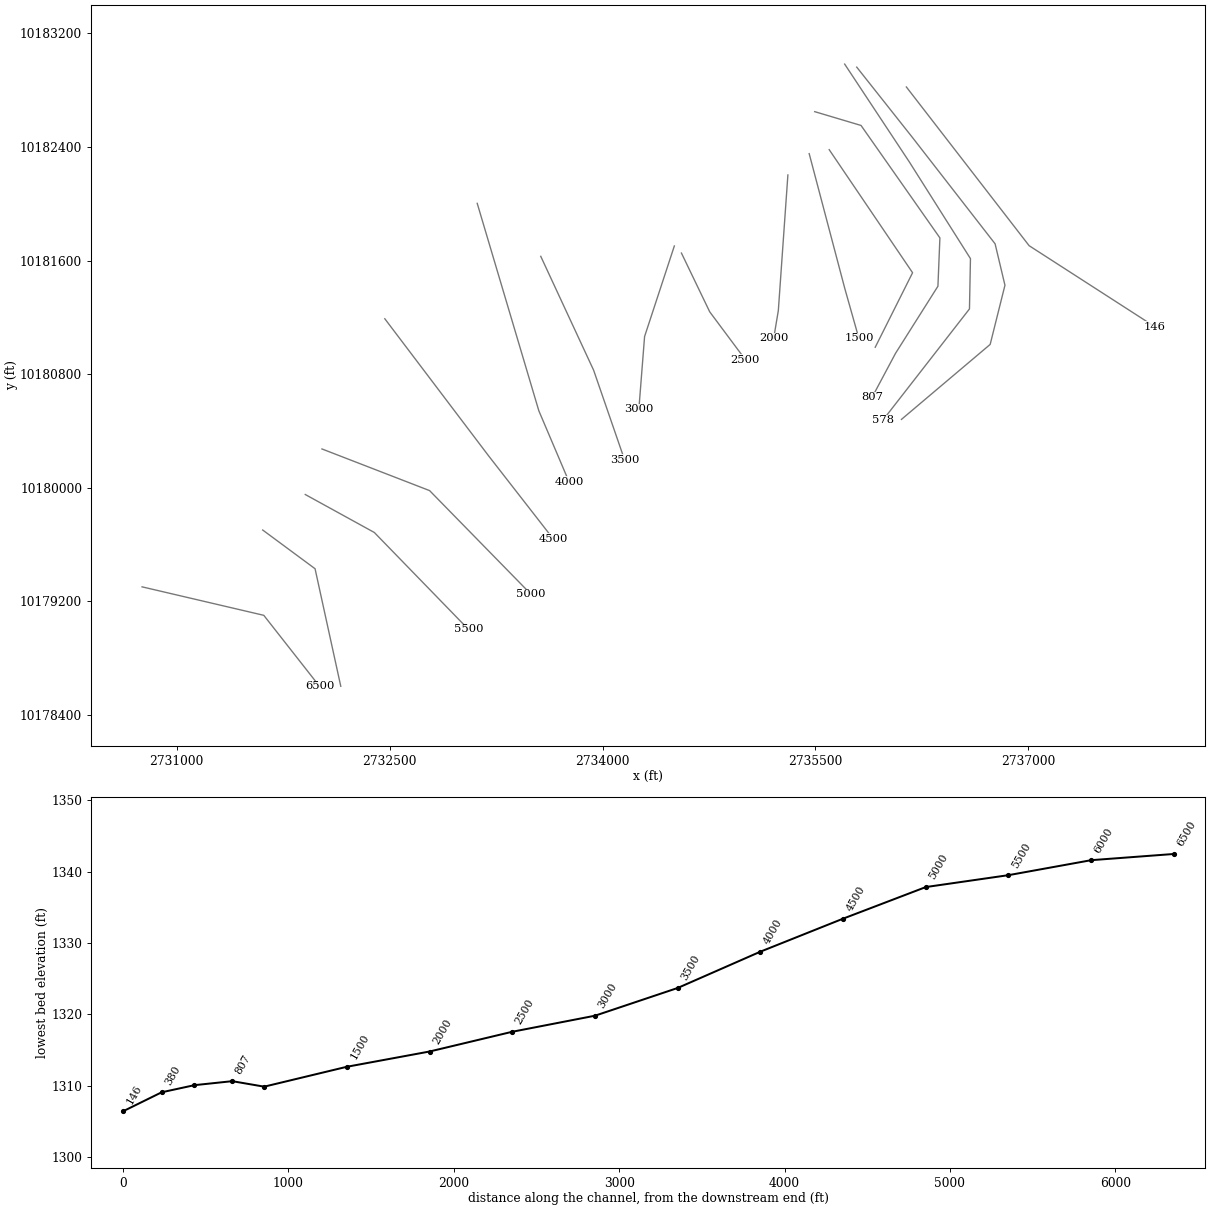
HEC-RAS study MARSCHALL BRANCH.prj: MARSCHALL BRANCH Base Level Engineering

--- MARSCHALL BRANCH.g01 (geometry) --- (continued)

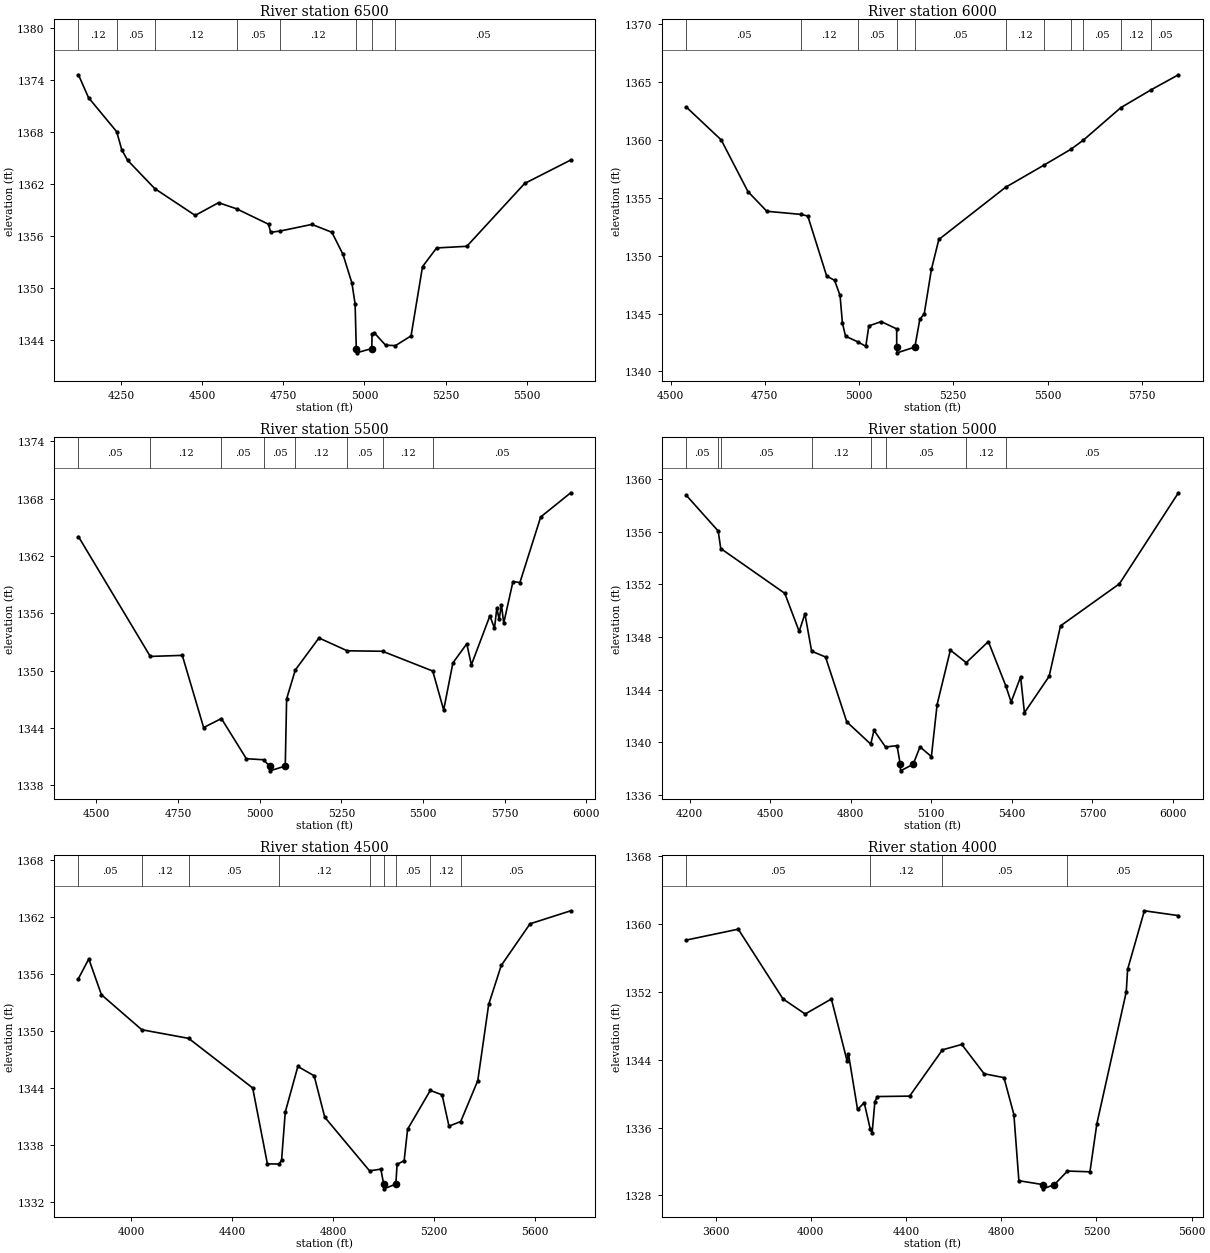
Type RM Length L Ch R = 1 ,6500    ,500,500,500
BEGIN DESCRIPTION:
MARSCHALL BRANCH 13.0
END DESCRIPTION:
XS GIS Cut Line= 3
      2730755.64     10179303.12      2731613.31     10179102.61
       2732005.7     10178603.09
#Sta/Elev= 30
  4119.2 1374.61  4150.1 1371.97    4237 1368.03  4252.8 1365.91  4270.6 1364.73
  4354.1 1361.46  4478.7 1358.36  4550.6 1359.83  4606.3 1359.12  4704.6 1357.34
    4711 1356.41  4739.7 1356.55  4838.1 1357.32  4899.7 1356.41  4933.8 1353.86
  4961.4 1350.54  4971.2 1348.12  4974.8 1342.98  4975.8 1342.48  5022.6 1342.98
  5023.3 1344.61  5029.6 1344.82  5064.9 1343.37  5095.4 1343.31  5143.5 1344.44
  5178.8 1352.44  5222.1  1354.6  5315.2 1354.79  5493.3 1362.05  5635.2 1364.76
#Mann= 8 ,-1 , 0
  4119.2     .12       0    4237     .05       0  4354.1     .12       0
  4606.3     .05       0  4739.7     .12       0  4974.8     .07       0
  5022.6     .12       0  5095.4     .05       0
Bank Sta=4974.8,5022.6
XS Rating Curve= 0 ,0
Exp/Cntr=0.3,0.1

Type RM Length L Ch R = 1 ,6000    ,500,500,500
BEGIN DESCRIPTION:
MARSCHALL BRANCH 12.0
END DESCRIPTION:
XS GIS Cut Line= 3
      2731605.67     10179703.12      2731974.46     10179430.69
      2732155.69      10178603.1
#Sta/Elev= 30
  4541.5 1362.87  4634.4 1360.02  4705.4 1355.55  4755.5 1353.85  4845.7 1353.58
  4864.1 1353.44  4914.2 1348.25  4935.1 1347.88  4949.7 1346.57  4955.9 1344.21
  4964.2 1343.05  4996.7 1342.56    5018 1342.18  5026.1 1343.94  5058.9 1344.31
  5099.9 1343.68    5100 1342.11    5101 1341.61  5148.1 1342.11  5161.3 1344.51
    5173 1344.98    5192 1348.82  5211.7 1351.41  5388.7 1355.92  5491.7 1357.86
  5561.5  1359.2  5594.8 1359.99  5694.5 1362.81  5775.3 1364.36  5847.2 1365.65
#Mann= 11 ,-1 , 0
  4541.5     .05       0  4845.7     .12       0  4996.7     .05       0
    5100     .05       0  5148.1     .05       0  5388.7     .12       0
  5491.7     .05       0  5561.5     .12       0  5594.8     .05       0
  5694.5     .12       0  5775.3     .05       0
Bank Sta=5100,5148.1
XS Rating Curve= 0 ,0
Exp/Cntr=0.3,0.1

Type RM Length L Ch R = 1 ,5500    ,500,500,500
BEGIN DESCRIPTION:
MARSCHALL BRANCH 11.0
END DESCRIPTION:
XS GIS Cut Line= 3
      2731905.65     10179953.13      2732392.12     10179685.78
      2733055.67     10179003.13
#Sta/Elev= 30
  4444.9 1364.01  4664.8 1351.48  4762.8 1351.59  4828.1 1344.04  4882.5 1344.98
  4958.9 1340.78  5011.5 1340.67  5029.8 1340.01  5030.8 1339.51    5078 1340.01
  5082.2 1347.04  5108.8 1350.06  5181.2 1353.41  5267.8 1352.07  5375.9 1352.02
  5529.6 1349.95    5563 1345.88  5591.3  1350.8  5633.7  1352.8  5647.9  1350.6
  5704.5 1355.72  5718.6 1354.43  5725.8 1356.54  5732.8 1355.37  5739.9 1356.87
  5746.9 1354.97  5775.2 1359.31  5796.5 1359.21  5860.1 1366.07    5952  1368.6
#Mann= 8 ,-1 , 0
  4444.9     .05       0  4664.8     .12       0  4882.5     .05       0
  5011.5     .05       0  5108.8     .12       0  5267.8     .05       0
  5375.9     .12       0  5529.6     .05       0
Bank Sta=5029.8,5078
XS Rating Curve= 0 ,0
Exp/Cntr=0.3,0.1

Type RM Length L Ch R = 1 ,5000    ,500,500,500
BEGIN DESCRIPTION:
MARSCHALL BRANCH 10.0
END DESCRIPTION:
XS GIS Cut Line= 3
      2732023.16     10180273.93      2732781.43     10179980.69
      2733495.17     10179251.59
#Sta/Elev= 30
    4187 1358.76  4306.3 1356.04  4315.8 1354.71  4554.3 1351.31  4607.9 1348.42
  4629.3 1349.75  4654.3 1346.92    4706 1346.48  4785.1 1341.56  4874.3 1339.87
  4886.6 1340.91  4929.5 1339.65  4972.4 1339.75  4984.3 1338.34  4985.3 1337.84
  5032.5 1338.34  5057.9 1339.66  5100.3 1338.92  5121.6 1342.87    5171    1347
  5230.1 1346.05  5312.5 1347.65  5377.8 1344.27  5397.3 1343.06  5432.6 1344.97
  5446.8 1342.25  5538.8 1345.01  5581.2 1348.84  5800.4 1352.03  6020.3 1358.94
#Mann= 8 ,-1 , 0
    4187     .05       0  4306.3     .12       0  4315.8     .05       0
  4654.3     .12       0  4874.3     .05       0  4929.5     .05       0
  5230.1     .12       0  5377.8     .05       0
Bank Sta=4984.3,5032.5
XS Rating Curve= 0 ,0
Exp/Cntr=0.3,0.1

Type RM Length L Ch R = 1 ,4500    ,500,500,500
BEGIN DESCRIPTION:
MARSCHALL BRANCH 9.0
END DESCRIPTION:
XS GIS Cut Line= 3
      2732465.87     10181190.62      2733195.41     10180227.66
      2733651.06     10179642.68
#Sta/Elev= 30
  3791.9 1355.51  3832.8 1357.57  3882.8 1353.81  4042.6 1350.13  4228.5 1349.22
  4481.9 1344.01  4540.2 1336.03  4586.7 1336.02  4596.4 1336.43  4610.9 1341.47
  4660.8 1346.27  4725.3 1345.29  4767.3 1340.94  4944.8  1335.3  4989.5 1335.48
  5000.7 1333.91  5001.7 1333.41  5048.9 1333.91  5053.8 1335.98  5081.8 1336.37
  5095.4 1339.67  5185.3 1343.75    5232 1343.29  5259.3    1340  5305.8 1340.48
  5373.4 1344.78  5416.6 1352.79  5466.3 1356.88  5580.3 1361.26  5741.5 1362.63
#Mann= 9 ,-1 , 0
  3791.9     .05       0  4042.6     .12       0  4228.5     .05       0
  4586.7     .12       0  4944.8     .05       0  5000.7     .05       0
  5048.9     .05       0  5185.3     .12       0  5305.8     .05       0
Bank Sta=5000.7,5048.9
XS Rating Curve= 0 ,0
Exp/Cntr=0.3,0.1

Type RM Length L Ch R = 1 ,4000    ,500,500,500
BEGIN DESCRIPTION:
MARSCHALL BRANCH 8.0
END DESCRIPTION:
XS GIS Cut Line= 3
      2733116.93     10182003.11      2733551.06     10180542.56
      2733764.26     10180041.54
#Sta/Elev= 30
  3476.3 1358.13  3695.1 1359.42  3883.2 1351.19  3976.3 1349.41  4086.4 1351.18
  4152.8 1343.84    4158 1344.73  4196.4 1338.15  4224.4 1338.94  4249.3 1335.89
  4257.6 1335.36  4269.2 1339.07  4279.6 1339.67  4415.2 1339.72    4553 1345.18
  4634.3 1345.82  4728.2 1342.36  4811.6  1341.9  4853.2 1337.55  4874.2 1329.74
  4975.1 1329.28  4976.1 1328.78  5023.5 1329.28  5078.3 1330.88  5172.8 1330.79
  5201.9 1336.47  5325.4 1352.02    5331 1354.67  5401.5 1361.59  5544.5 1361.02
#Mann= 4 ,-1 , 0
  3476.3     .05       0  4249.3     .12       0    4553     .05       0
  5078.3     .05       0
Bank Sta=4975.1,5023.5
XS Rating Curve= 0 ,0
Exp/Cntr=0.3,0.1

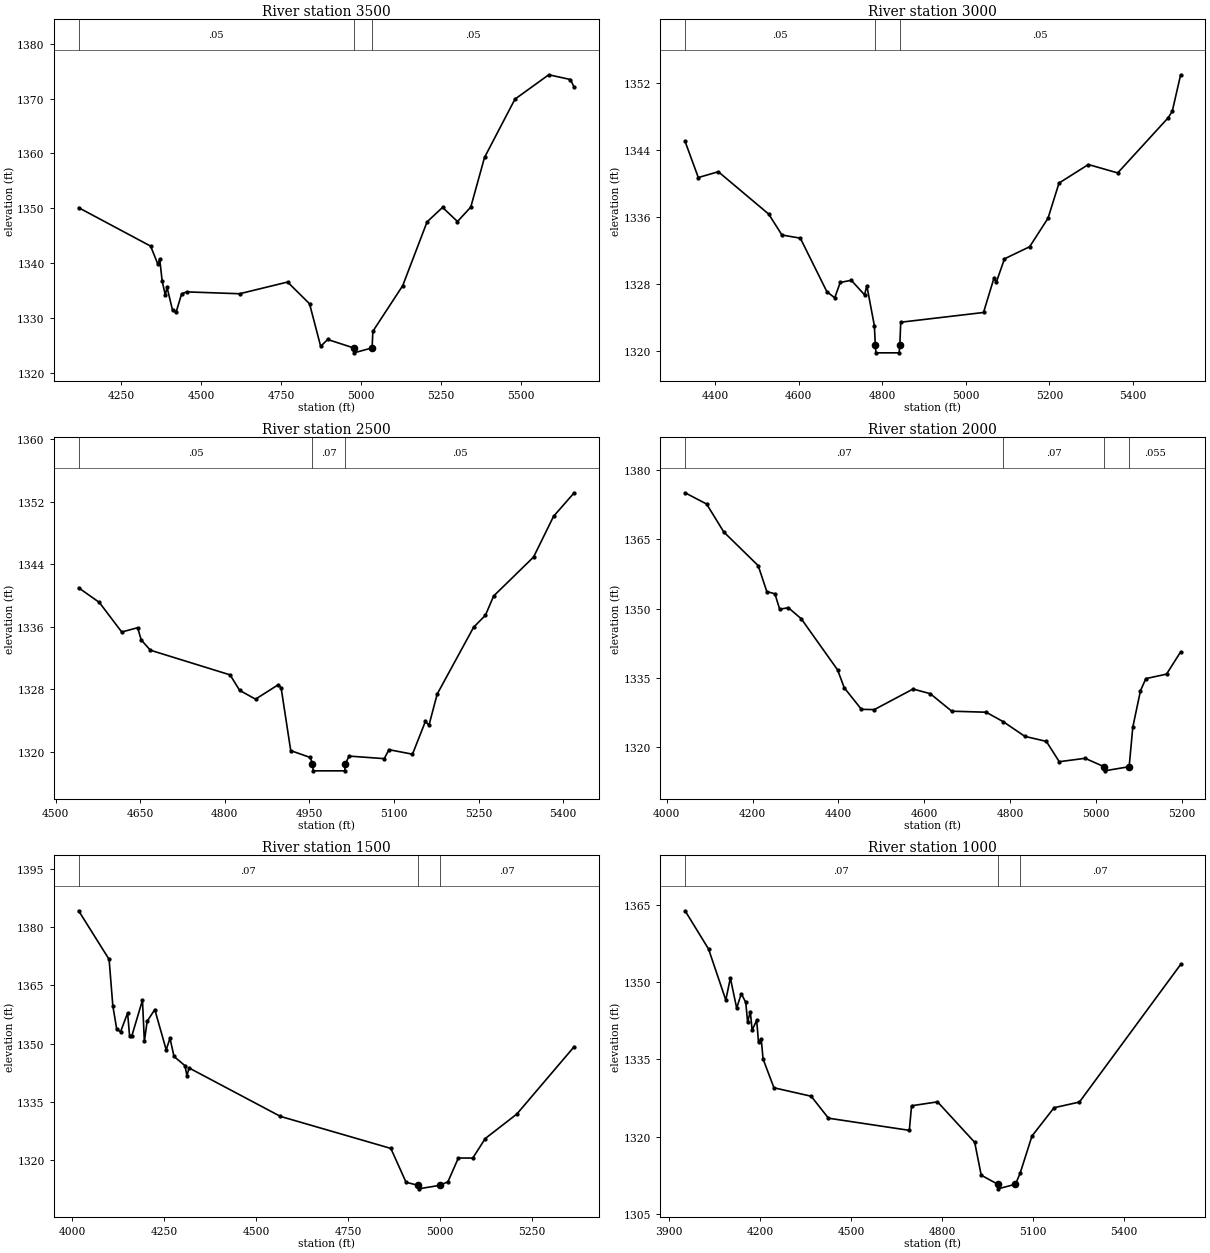
Type RM Length L Ch R = 1 ,3500    ,500,500,500
BEGIN DESCRIPTION:
MARSCHALL BRANCH 7.0
END DESCRIPTION:
XS GIS Cut Line= 3
      2733564.61     10181630.07      2733937.05     10180828.35
      2734154.84     10180197.91
#Sta/Elev= 30
    4116 1350.12  4341.4 1343.12  4364.3 1339.78  4369.8  1340.8  4377.3 1336.82
  4387.1 1334.22  4392.7 1335.62    4410 1331.43  4421.4 1331.15  4438.4 1334.43
  4454.5 1334.79  4619.9 1334.45    4770 1336.58  4838.7 1332.63  4873.5 1324.88
  4895.5 1326.12  4976.6 1324.59  4977.9 1323.69  5034.5 1324.59  5036.9 1327.61
  5130.4 1335.93  5206.6 1347.54  5255.1 1350.17  5301.8  1347.6  5343.4 1350.23
  5386.4 1359.27  5481.6 1369.88  5587.4 1374.32  5655.2 1373.46    5667 1372.04
#Mann= 3 ,-1 , 0
    4116     .05       0  4976.6     .07       0  5034.5     .05       0
Bank Sta=4976.6,5034.5
XS Rating Curve= 0 ,0
Exp/Cntr=0.3,0.1

Type RM Length L Ch R = 1 ,3000    ,500,500,500
BEGIN DESCRIPTION:
MARSCHALL BRANCH 6.0
END DESCRIPTION:
XS GIS Cut Line= 3
      2734505.69     10181703.13      2734296.03     10181065.41
      2734255.68      10180553.1
#Sta/Elev= 30
  4328.7    1345  4360.3  1340.7  4408.2 1341.39  4528.7 1336.34  4560.3 1333.85
  4604.3 1333.47  4667.9 1327.08  4686.6 1326.36  4699.7 1328.19  4726.2 1328.45
    4758 1326.71  4763.3 1327.82  4781.4 1323.03  4783.7  1320.7  4785.1  1319.8
  4840.7  1319.8  4842.2  1320.7  4844.5 1323.45  5042.4 1324.61  5067.8 1328.76
  5072.8 1328.19  5092.6 1331.01  5152.8 1332.45  5196.7 1335.85    5223 1340.04
  5293.2 1342.25  5363.4 1341.25  5483.8 1347.81  5493.8 1348.59  5513.9 1352.95
#Mann= 3 ,-1 , 0
  4328.7     .05       0  4783.7     .07       0  4842.2     .05       0
Bank Sta=4783.7,4842.2
XS Rating Curve= 0 ,0
Exp/Cntr=0.3,0.1

Type RM Length L Ch R = 1 ,2500    ,500,500,500
BEGIN DESCRIPTION:
MARSCHALL BRANCH 5.0
END DESCRIPTION:
XS GIS Cut Line= 3
      2734555.68     10181653.12      2734754.92      10181239.4
      2735005.69      10180903.1
#Sta/Elev= 30
  4540.8 1340.99  4577.5 1339.12  4617.2 1335.33  4645.4 1335.88  4651.8 1334.31
    4668    1333  4809.3 1329.84  4826.4 1327.85  4854.5 1326.73  4894.2 1328.55
  4899.8 1328.21  4916.9 1320.14  4951.5 1319.26  4955.4 1318.45  4956.8 1317.55
  5012.6 1317.55    5014 1318.45  5020.2 1319.44  5082.7 1319.11  5091.1 1320.26
  5132.8 1319.68  5155.7 1323.88    5162 1323.39  5176.6 1327.38  5241.2 1335.94
  5262.1 1337.47  5276.7 1339.94  5347.5 1344.93    5383 1350.15  5419.5 1353.16
#Mann= 3 ,-1 , 0
  4540.8     .05       0  4955.4     .07       0    5014     .05       0
Bank Sta=4955.4,5014
XS Rating Curve= 0 ,0
Exp/Cntr=0.3,0.1

Type RM Length L Ch R = 1 ,2000    ,500,500,500
BEGIN DESCRIPTION:
MARSCHALL BRANCH 4.0
END DESCRIPTION:
XS GIS Cut Line= 3
      2735305.68     10182203.07      2735238.33     10181248.34
      2735205.69     10181053.15
#Sta/Elev= 30
  4042.9 1375.11    4093 1372.67  4133.1  1366.6  4213.3  1359.3  4233.3 1353.68
  4252.2 1353.19  4263.4 1349.84  4283.5 1350.18  4313.5 1347.79  4398.4 1336.67
  4413.8 1332.81  4453.9 1328.12    4484 1328.07  4574.2 1332.53  4614.3 1331.52
  4664.4 1327.72  4744.6  1327.5  4784.7 1325.43  4834.8 1322.26  4884.9 1321.17
    4915 1316.76  4975.2  1317.5  5019.3 1315.68  5020.7 1314.78  5077.9 1315.68
  5086.4 1324.26  5104.3 1332.17  5116.8 1334.79    5165 1335.76  5197.9 1340.59
#Mann= 4 ,-1 , 0
  4042.9     .07       0  4784.7     .07       0  5019.3    .055       0
  5077.9    .055       0
Bank Sta=5019.3,5077.9
XS Rating Curve= 0 ,0
Exp/Cntr=0.3,0.1

Type RM Length L Ch R = 1 ,1500    ,500,500,500
BEGIN DESCRIPTION:
MARSCHALL BRANCH 3.0
END DESCRIPTION:
XS GIS Cut Line= 3
      2735455.68     10182353.12       2735706.5       10181404.
      2735805.67     10181053.15
#Sta/Elev= 30
  4018.3 1384.18  4101.1 1371.67  4111.2 1359.73  4121.7 1353.79  4132.1 1353.01
  4151.4 1357.89  4156.6 1352.07  4163.1 1352.07  4191.7 1361.17  4196.9 1350.61
  4204.5 1355.76  4225.2 1358.77  4256.2 1348.41  4266.5  1351.4  4277.4  1346.7
  4307.3 1344.32  4312.5  1341.7  4318.3 1343.74  4566.5 1331.28  4866.5 1323.04
  4907.8 1314.34  4940.5 1313.54  4941.9 1312.64  4999.2 1313.54  5021.7 1314.47
  5049.9 1320.57  5089.1 1320.56  5123.1 1325.59  5208.8 1331.88  5364.6 1349.22
#Mann= 3 ,-1 , 0
  4018.3     .07       0  4940.5     .07       0  4999.2     .07       0
Bank Sta=4940.5,4999.2
XS Rating Curve= 0 ,0
Exp/Cntr=0.3,0.1

Type RM Length L Ch R = 1 ,1000    ,193,193,193
BEGIN DESCRIPTION:
MARSCHALL BRANCH 2.0
END DESCRIPTION:
XS GIS Cut Line= 3
      2735596.67     10182381.11       2736184.1     10181514.67
      2735921.01     10180990.04
#Sta/Elev= 30
  3953.2 1363.81  4030.5 1356.39  4087.4 1346.49  4102.4 1350.76  4123.3 1344.91
  4138.3 1347.71  4153.2 1346.05  4159.3  1342.2  4168.2 1344.25  4174.2 1340.63
  4189.2 1342.55  4195.2 1338.26  4204.1 1338.99  4210.2 1335.06  4246.1 1329.46
  4368.9 1327.82  4425.8 1323.56  4692.4  1321.2  4699.8 1325.97  4785.3 1326.73
    4908 1318.87  4929.4  1312.5  4983.7 1310.75  4985.1 1309.85  5042.4 1310.75
  5057.8 1312.89  5096.8  1320.1  5169.5 1325.59  5253.2 1326.69  5586.9 1353.39
#Mann= 3 ,-1 , 0
  3953.2     .07       0  4983.7     .07       0  5057.8     .07       0
Bank Sta=4983.7,5042.4
XS Rating Curve= 0 ,0
Exp/Cntr=0.3,0.1

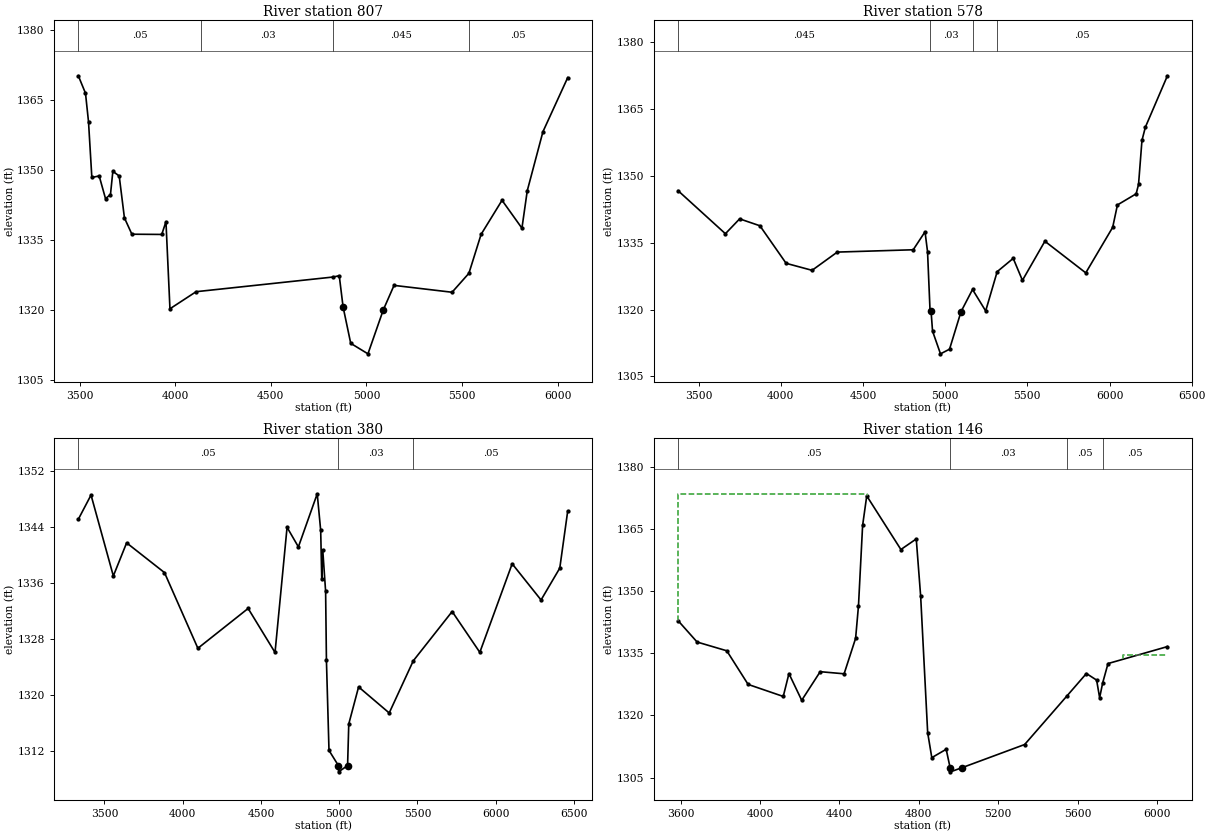
Type RM Length L Ch R = 1 ,807     ,229,229,229
BEGIN DESCRIPTION:
Mapping XS 7a142d09
END DESCRIPTION:
XS GIS Cut Line= 6
      2735494.62      10182648.8      2735821.02     10182551.57
      2736376.58      10181759.9      2736362.69     10181419.63
      2736064.08      10180947.4      2735898.25     10180636.47
#Sta/Elev= 30
  3493.2 1370.17  3530.7 1366.43  3546.5 1360.32  3563.9 1348.39  3602.3 1348.72
  3635.4 1343.86  3661.3 1344.73  3673.8 1349.71    3707 1348.71  3734.3 1339.74
  3773.3 1336.24  3929.6 1336.19  3951.5 1338.93  3972.4 1320.27  4109.3 1323.93
  4827.7 1327.08  4857.8 1327.36  4877.8 1320.68  4917.8 1312.87  5007.9 1310.62
    5088 1320.02  5144.3 1325.28  5447.8 1323.81  5535.9 1327.87  5599.5  1336.2
  5709.1  1343.5  5813.2 1337.53  5841.1 1345.56    5923 1358.19  6052.6 1369.78
#Mann= 4 ,-1 , 0
  3493.2     .05       0  4137.3     .03       0  4827.7    .045       0
  5535.9     .05       0
Bank Sta=4877.8,5088
XS Rating Curve= 0 ,0
Exp/Cntr=0.3,0.1

Type RM Length L Ch R = 1 ,578     ,198,198,198
BEGIN DESCRIPTION:
Mapping XS 4c84ac10
END DESCRIPTION:
XS GIS Cut Line= 5
      2735705.61     10182983.56       2736161.3     10182294.63
      2736591.86     10181614.07      2736584.91      10181259.9
      2735974.95     10180476.65
#Sta/Elev= 30
  3374.1 1346.66  3662.4    1337  3749.1 1340.33  3872.5 1338.78    4032 1330.36
  4189.9 1328.79  4343.3 1332.88  4805.4  1333.4  4877.3 1337.43  4892.6 1332.97
  4907.8 1319.77  4913.8 1319.71  4923.1 1315.15  4971.4 1310.06  5026.4  1311.1
  5096.4 1319.52  5166.4 1324.49  5246.4 1319.68  5316.4 1328.49    5414 1331.47
  5470.1 1326.54  5606.7 1335.31  5855.5 1328.22  6019.3 1338.43  6048.2 1343.45
  6162.2 1345.95  6176.7 1348.06  6197.5 1357.92  6218.3  1360.9  6352.4 1372.42
#Mann= 4 ,-1 , 0
  3374.1    .045       0  4907.8     .03       0  5166.4    .045       0
  5316.4     .05       0
Bank Sta=4913.8,5096.4
XS Rating Curve= 0 ,0
Exp/Cntr=0.3,0.1

Type RM Length L Ch R = 1 ,380     ,234,234,234
BEGIN DESCRIPTION:
Mapping XS 9dc69405
END DESCRIPTION:
XS GIS Cut Line= 6
      2735790.66     10182962.26      2736182.14     10182468.24
      2736765.47     10181718.24      2736834.91     10181426.57
      2736730.75      10181009.9      2736105.76     10180482.13
#Sta/Elev= 30
  3332.8 1345.14    3414  1348.6  3556.6 1337.04  3641.5 1341.77  3883.5 1337.52
  4096.9 1326.71  4418.1  1332.4    4590 1326.11  4666.9 1343.99  4739.3 1341.19
  4859.7 1348.78  4881.8 1343.55  4888.6 1336.58    4895 1340.74  4913.3 1334.83
  4918.5    1325  4934.9 1312.12  4994.9 1309.96  4996.4 1309.06  5053.7 1309.96
  5061.3  1315.9  5124.1 1321.19  5319.7 1317.47  5473.6 1324.92    5722 1331.96
  5898.9 1326.13  6105.6 1338.78  6290.2 1333.61  6409.9 1338.16  6460.6 1346.32
#Mann= 3 ,-1 , 0
  3332.8     .05       0  4994.9     .03       0  5473.6     .05       0
Bank Sta=4994.9,5053.7
XS Rating Curve= 0 ,0
Exp/Cntr=0.3,0.1

Type RM Length L Ch R = 1 ,146     ,0,0,0
BEGIN DESCRIPTION:
MARSCHALL BRANCH 1.0
END DESCRIPTION:
XS GIS Cut Line= 3
      2736140.44     10182822.44      2737005.25       10181705.
      2737890.46     10181134.91
#Sta/Elev= 30
    3587 1342.86  3683.2 1337.69  3832.6 1335.58  3940.2 1327.47  4117.2 1324.57
  4145.9 1330.08  4210.2 1323.64  4303.4 1330.54  4423.9 1330.03  4481.8 1338.58
  4496.3 1346.45  4517.1 1365.81  4537.9 1372.93    4710    1360  4787.4 1362.55
  4809.6 1348.71  4844.9 1315.84  4865.7 1309.81  4938.2 1311.83    4958 1307.39
  4959.5 1306.39    5018 1307.39  5333.6 1312.98    5545  1324.6  5644.7  1330.1
  5696.2 1328.51  5711.4 1324.26  5726.8 1327.85  5753.6  1332.5  6052.9 1336.59
#Mann= 4 ,-1 , 0
    3587     .05       0    4958     .03       0    5545     .05       0
  5726.8     .05       0
#XS Ineff= 2 , 0
         4538.25 1373.44 5827.87         1334.59
Permanent Ineff=
       F       F
Bank Sta=4958,5018
XS Rating Curve= 0 ,0
Exp/Cntr=0.3,0.1
Stream Node=MARSCHALL BRANCH,Reach-1         , 0 , 0 ,Upstream end
Stream Node=MARSCHALL BRANCH,Reach-1         , 0 , 1 ,Downstream end

Chan Stop Cuts=-1
Use User Specified Reach Order=0
Composite Channel Slope=5