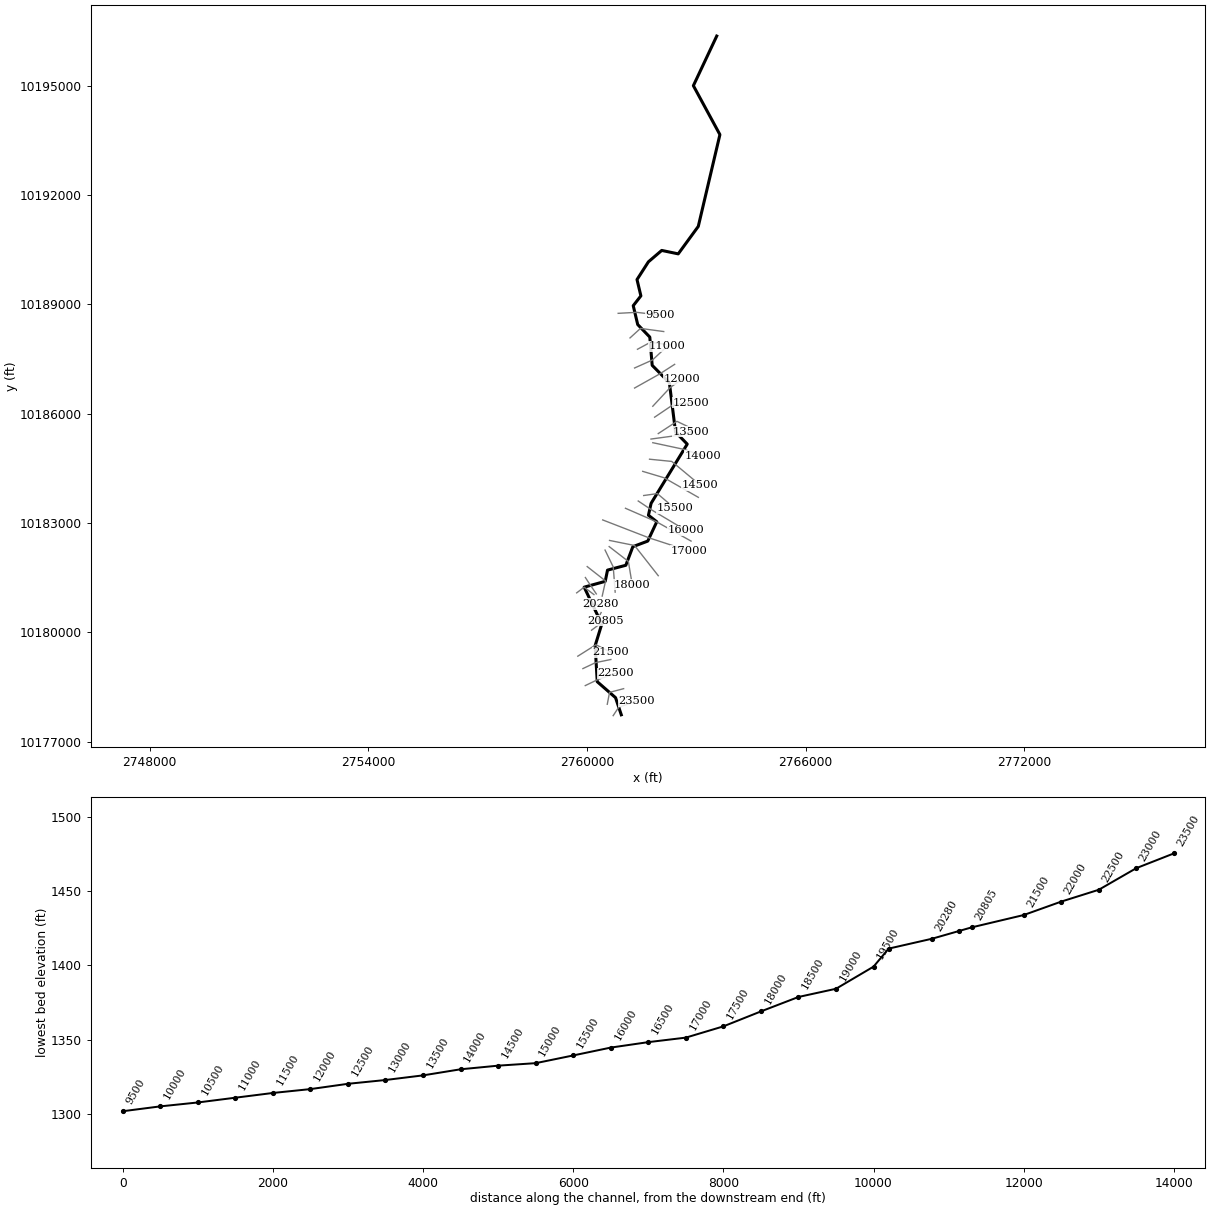
--- PRAIRIE MT SPRING BRANCH.prj (project) ---

Proj Title=PRAIRIE MT SPRING BRANCH Base Level Engineering
Current Plan=p01
Default Exp/Contr=0.3,0.1
English Units
Geom File=g01
Flow File=f01
Plan File=p01
BEGIN DESCRIPTION:
PRAIRIE MT SPRING BRANCH
END DESCRIPTION:

--- PRAIRIE MT SPRING BRANCH.p01 (plan) ---

Plan Title=Multiple Run
Short Identifier=Multiple
Geom File=g01
Flow File=f01
Subcritical Flow
K Sum by GR= 0
Std Step Tol= 0.01
Critical Tol= 0.01
Num of Std Step Trials= 20
Max Error Tol= 0.3
Flow Tol Ratio= 0.001
Split Flow NTrial= 30
Split Flow Tol= 0.02
Split Flow Ratio= 0.02
Log Output Level= 0
Friction Slope Method= 1
Unsteady Friction Slope Method= 2
Unsteady Bridges Friction Slope Method= 1
Parabolic Critical Depth
Global Vel Dist=  1 , 1 , 1
Global Log Level= 0
CheckData=True
Encroach Param= -1, 0, 0, 0
BEGIN DESCRIPTION:
Multiple Run
END DESCRIPTION:

--- PRAIRIE MT SPRING BRANCH.f01 (steady flow) ---

Flow Title=Multiple
Number of Profiles=7
Profile Names=10-year,25-year,50-year,1pct_min,100-year,1pct_plu,500-year
River Rch & RM= PRAIRIE MT SPRIN,Reach-1,23500
     458     745    1036     764    1391    2532    1927
River Rch & RM= PRAIRIE MT SPRIN,Reach-1,14000
     597     993    1309     915    1766    3409    2438
River Rch & RM= PRAIRIE MT SPRIN,Reach-1,9500
     791    1332    1901    1357    2597    4969    3574
River Rch & RM= PRAIRIE MT SPRIN,Reach-1,8500
    1103    1906    2672    1828    3686    7432    5063
River Rch & RM= PRAIRIE MT SPRIN,Reach-1,1500
    1187    2062    2866    1942    3961    8079    5436
Boundary for River Rch & Prof#=PRAIRIE MT SPRIN,Reach-1,1
Up Type=0
Dn Type=3
Dn Slope=0.005
Boundary for River Rch & Prof#=PRAIRIE MT SPRIN,Reach-1,2
Up Type=0
Dn Type=3
Dn Slope=0.005
Boundary for River Rch & Prof#=PRAIRIE MT SPRIN,Reach-1,3
Up Type=0
Dn Type=3
Dn Slope=0.005
Boundary for River Rch & Prof#=PRAIRIE MT SPRIN,Reach-1,4
Up Type=0
Dn Type=3
Dn Slope=0.005
Boundary for River Rch & Prof#=PRAIRIE MT SPRIN,Reach-1,5
Up Type=0
Dn Type=3
Dn Slope=0.005
Boundary for River Rch & Prof#=PRAIRIE MT SPRIN,Reach-1,6
Up Type=0
Dn Type=3
Dn Slope=0.005
Boundary for River Rch & Prof#=PRAIRIE MT SPRIN,Reach-1,7
Up Type=0
Dn Type=3
Dn Slope=0.005

--- PRAIRIE MT SPRING BRANCH.g01 (geometry) ---

Geom Title=Existing Conditions

River Reach=PRAIRIE MT SPRIN,Reach-1
Reach XY= 30
      2760941.00     10177736.00      2760783.25     10178206.00
      2760281.25     10178644.00      2760223.50     10179633.00
      2760405.75     10180226.00      2759922.50     10181238.00
      2760500.50     10181398.00      2760563.25     10181706.00
      2761065.25     10181839.00      2761258.25     10182349.00
      2761667.75     10182503.00      2761915.25     10183033.00
      2761686.00     10183212.00      2761759.00     10183539.00
      2762750.75     10185164.00      2762429.75     10185495.00
      2762261.00     10186848.00      2761789.00     10187326.00
      2761723.50     10188101.00      2761391.75     10188445.00
      2761269.25     10188963.00      2761478.75     10189232.00
      2761372.50     10189679.00      2761685.00     10190166.00
      2762050.50     10190479.00      2762503.75     10190385.00
      2763053.75     10191138.00      2763647.50     10193657.00
      2762919.25     10195000.00      2763560.25     10196362.00

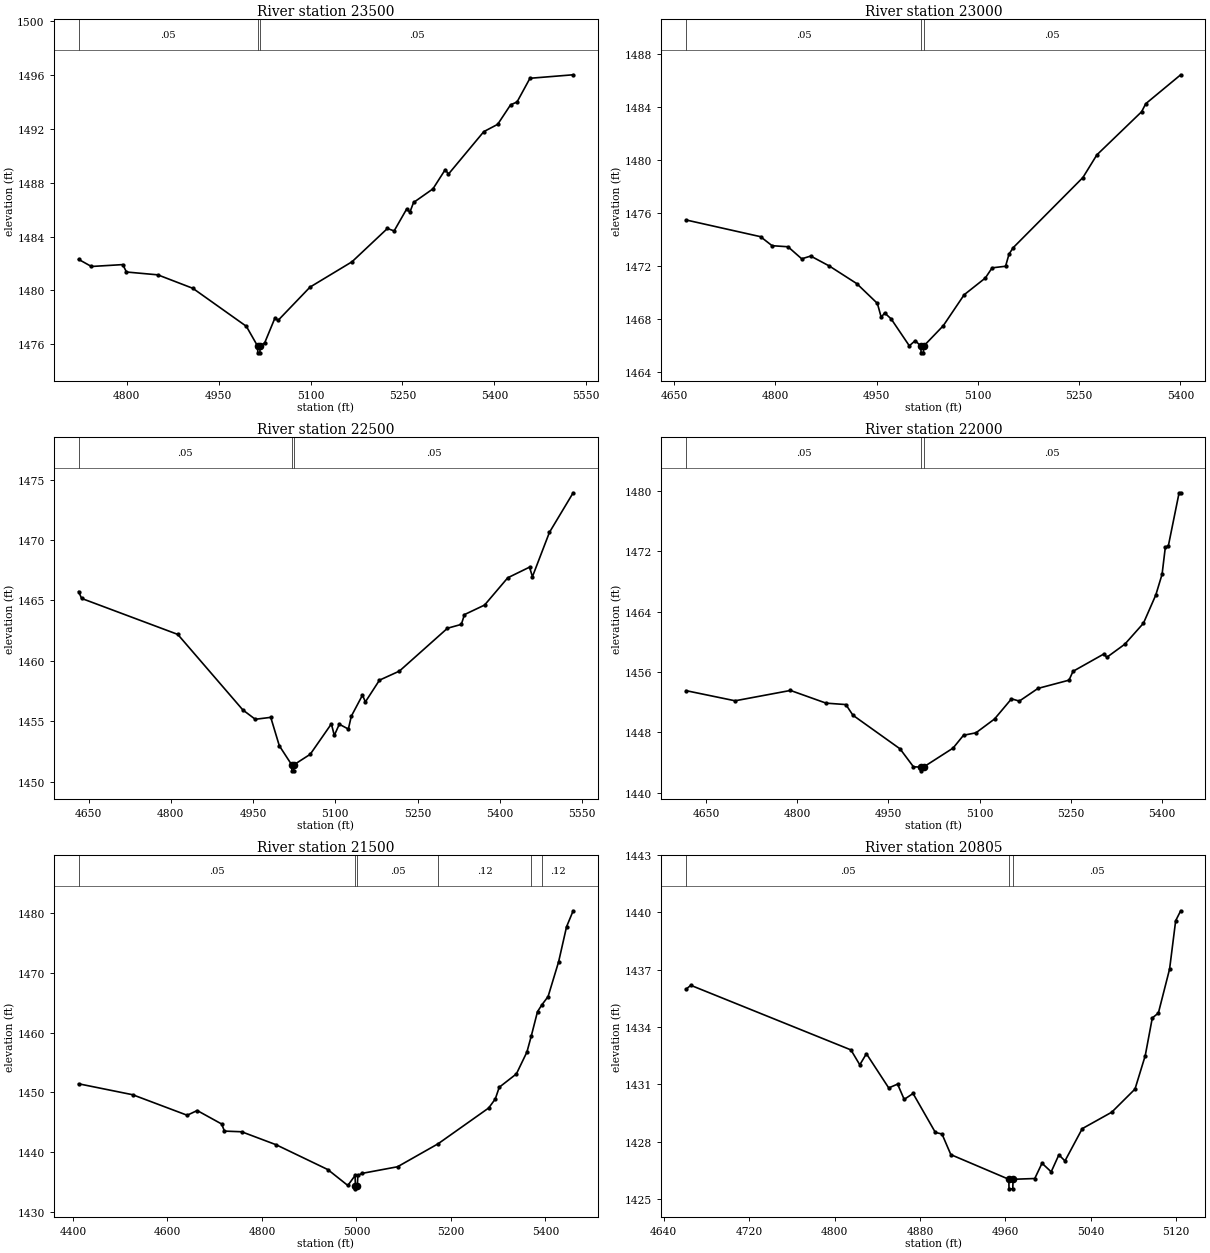
Type RM Length L Ch R = 1,23500,500,500,500
BEGIN DESCRIPTION:
PRAIRIE MT SPRING BRANCH 47.0
END DESCRIPTION:
XS GIS Cut Line= 3
      2760717.99     10177712.37      2760871.69     10177944.50
      2761372.44     10178113.49
#Sta/Elev= 30
  4721.6 1482.31  4742.5 1481.78  4793.7 1481.92  4799.7 1481.37  4850.8 1481.16
  4908.0 1480.16  4995.3 1477.34  5013.7 1475.87  5013.9 1475.37  5017.4 1475.37
  5017.7 1475.87  5025.3 1476.12  5041.9 1477.95  5047.1 1477.78  5099.2 1480.25
  5167.7 1482.13  5225.4 1484.60  5236.4 1484.42  5256.9 1486.05  5262.1 1485.81
  5268.1 1486.53  5299.7 1487.54  5319.8 1488.97  5325.1 1488.64  5382.7 1491.79
  5405.3 1492.33  5426.4 1493.78  5436.9 1493.99  5458.0 1495.75  5528.5 1496.01
#Mann=3,-1,0
  4721.6    0.05       0  5013.7    0.03       0  5017.7    0.05       0
Bank Sta=5013.7,5017.7
Exp/Cntr=0.3,0.1

Type RM Length L Ch R = 1,23000,500,500,500
BEGIN DESCRIPTION:
PRAIRIE MT SPRING BRANCH 46.0
END DESCRIPTION:
XS GIS Cut Line= 3
      2760556.54     10178024.90      2760618.64     10178351.04
      2761005.70     10178453.12
#Sta/Elev= 30
  4668.0 1475.47  4778.2 1474.21  4795.3 1473.53  4818.9 1473.45  4839.2 1472.54
  4852.5 1472.75  4880.0 1472.00  4920.7 1470.67  4951.2 1469.18  4956.9 1468.13
  4962.0 1468.46  4971.6 1468.01  4998.5 1465.98  5007.3 1466.37  5015.6 1465.95
  5015.9 1465.45  5019.4 1465.45  5019.6 1465.95  5048.7 1467.49  5079.7 1469.83
  5111.0 1471.09  5121.1 1471.86  5141.0 1471.98  5146.1 1472.89  5152.1 1473.37
  5255.5 1478.67  5276.2 1480.38  5342.4 1483.63  5348.6 1484.24  5400.3 1486.42
#Mann=3,-1,0
  4668.0    0.05       0  5015.6    0.03       0  5019.6    0.05       0
Bank Sta=5015.6,5019.6
Exp/Cntr=0.3,0.1

Type RM Length L Ch R = 1,22500,500,500,500
BEGIN DESCRIPTION:
PRAIRIE MT SPRING BRANCH 45.0
END DESCRIPTION:
XS GIS Cut Line= 3
      2759952.63     10178537.22      2760284.41     10178696.88
      2760788.21     10178873.62
#Sta/Elev= 30
  4631.8 1465.74  4637.3 1465.17  4812.7 1462.19  4931.5 1455.93  4954.1 1455.16
  4982.3 1455.32  4997.9 1452.97  5020.5 1451.39  5020.8 1450.89  5024.3 1450.89
  5024.5 1451.39  5054.3 1452.26  5092.9 1454.78  5098.2 1453.82  5107.3 1454.75
  5123.9 1454.35  5129.2 1455.41  5149.6 1457.16  5154.9 1456.60  5180.6 1458.40
  5216.9 1459.15  5304.6 1462.70  5329.9 1463.02  5335.6 1463.83  5372.3 1464.62
  5414.6 1466.88  5454.3 1467.76  5459.6 1466.97  5490.6 1470.64  5533.9 1473.92
#Mann=3,-1,0
  4631.8    0.05       0  5020.5    0.03       0  5024.5    0.05       0
Bank Sta=5020.5,5024.5
Exp/Cntr=0.3,0.1

Type RM Length L Ch R = 1,22000,500,500,500
BEGIN DESCRIPTION:
PRAIRIE MT SPRING BRANCH 44.0
END DESCRIPTION:
XS GIS Cut Line= 3
      2759887.53     10179003.80      2760233.66     10179167.29
      2760655.72     10179253.12
#Sta/Elev= 30
  4617.2 1453.53  4697.8 1452.19  4788.9 1453.56  4847.4 1451.88  4880.0 1451.69
  4891.6 1450.28  4969.1 1445.83  4991.2 1443.45  5003.7 1443.42  5003.9 1442.92
  5007.7 1443.42  5056.3 1445.93  5073.5 1447.63  5093.9 1447.95  5124.5 1449.78
  5152.4 1452.45  5165.3 1452.15  5196.0 1453.83  5247.0 1454.92  5253.6 1456.09
  5304.2 1458.38  5309.3 1457.95  5338.8 1459.68  5369.4 1462.45  5389.8 1466.20
  5400.1 1468.94  5405.4 1472.49  5410.5 1472.73  5428.1 1479.72  5430.7 1479.72
#Mann=3,-1,0
  4617.2    0.05       0  5003.7    0.05       0  5007.7    0.05       0
Bank Sta=5003.7,5007.7
Exp/Cntr=0.3,0.1

Type RM Length L Ch R = 1,21500,695,695,695
BEGIN DESCRIPTION:
PRAIRIE MT SPRING BRANCH 43.0
END DESCRIPTION:
XS GIS Cut Line= 3
      2759747.82     10179344.47      2760245.21     10179658.26
      2760655.70     10179453.11
#Sta/Elev= 30
  4411.9 1451.43  4526.4 1449.60  4641.8 1446.17  4663.0 1446.96  4714.7 1444.71
  4720.7 1443.52  4757.1 1443.41  4830.1 1441.24  4939.5 1437.09  4981.9 1434.43
  4997.2 1436.10  4997.9 1434.37  4998.1 1433.87  5001.9 1434.37  5003.2 1436.10
  5011.7 1436.45  5087.1 1437.56  5173.1 1441.41  5280.0 1447.38  5294.0 1448.89
  5302.4 1450.85  5338.7 1453.08  5361.0 1456.74  5370.1 1459.38  5383.4 1463.49
  5392.5 1464.61  5405.8 1466.01  5428.1 1471.83  5444.9 1477.68  5458.9 1480.35
#Mann=6,-1,0
  4411.9    0.05       0  4997.9    0.05       0  5001.9    0.05       0
  5173.1    0.12       0  5370.1    0.05       0  5392.5    0.12       0
Bank Sta=4997.9,5001.9
Exp/Cntr=0.3,0.1

Type RM Length L Ch R = 1,20805,173,173,173
BEGIN DESCRIPTION:
PRAIRIE MT SPRING BRANCH 42.0
END DESCRIPTION:
XS GIS Cut Line= 3
      2760124.67     10180057.32      2760395.64     10180261.20
      2760504.86     10180320.33
#Sta/Elev= 30
  4660.9 1435.99  4665.3 1436.19  4815.3 1432.81  4823.6 1432.03  4829.8 1432.61
  4850.7 1430.82  4859.0 1431.02  4865.2 1430.22  4873.5 1430.53  4894.4 1428.49
  4900.6 1428.41  4908.9 1427.33  4963.2 1426.04  4963.4 1425.54  4966.9 1425.54
  4967.2 1426.04  4987.5 1426.08  4994.3 1426.88  5002.9 1426.43  5010.1 1427.32
  5015.8 1427.00  5032.0 1428.69  5059.6 1429.55  5081.4 1430.76  5091.0 1432.51
  5097.6 1434.48  5103.3 1434.74  5113.8 1437.04  5119.5 1439.57  5124.2 1440.09
#Mann=3,-1,0
  4660.9    0.05       0  4963.2    0.03       0  4967.2    0.05       0
Bank Sta=4963.2,4967.2
Exp/Cntr=0.3,0.1

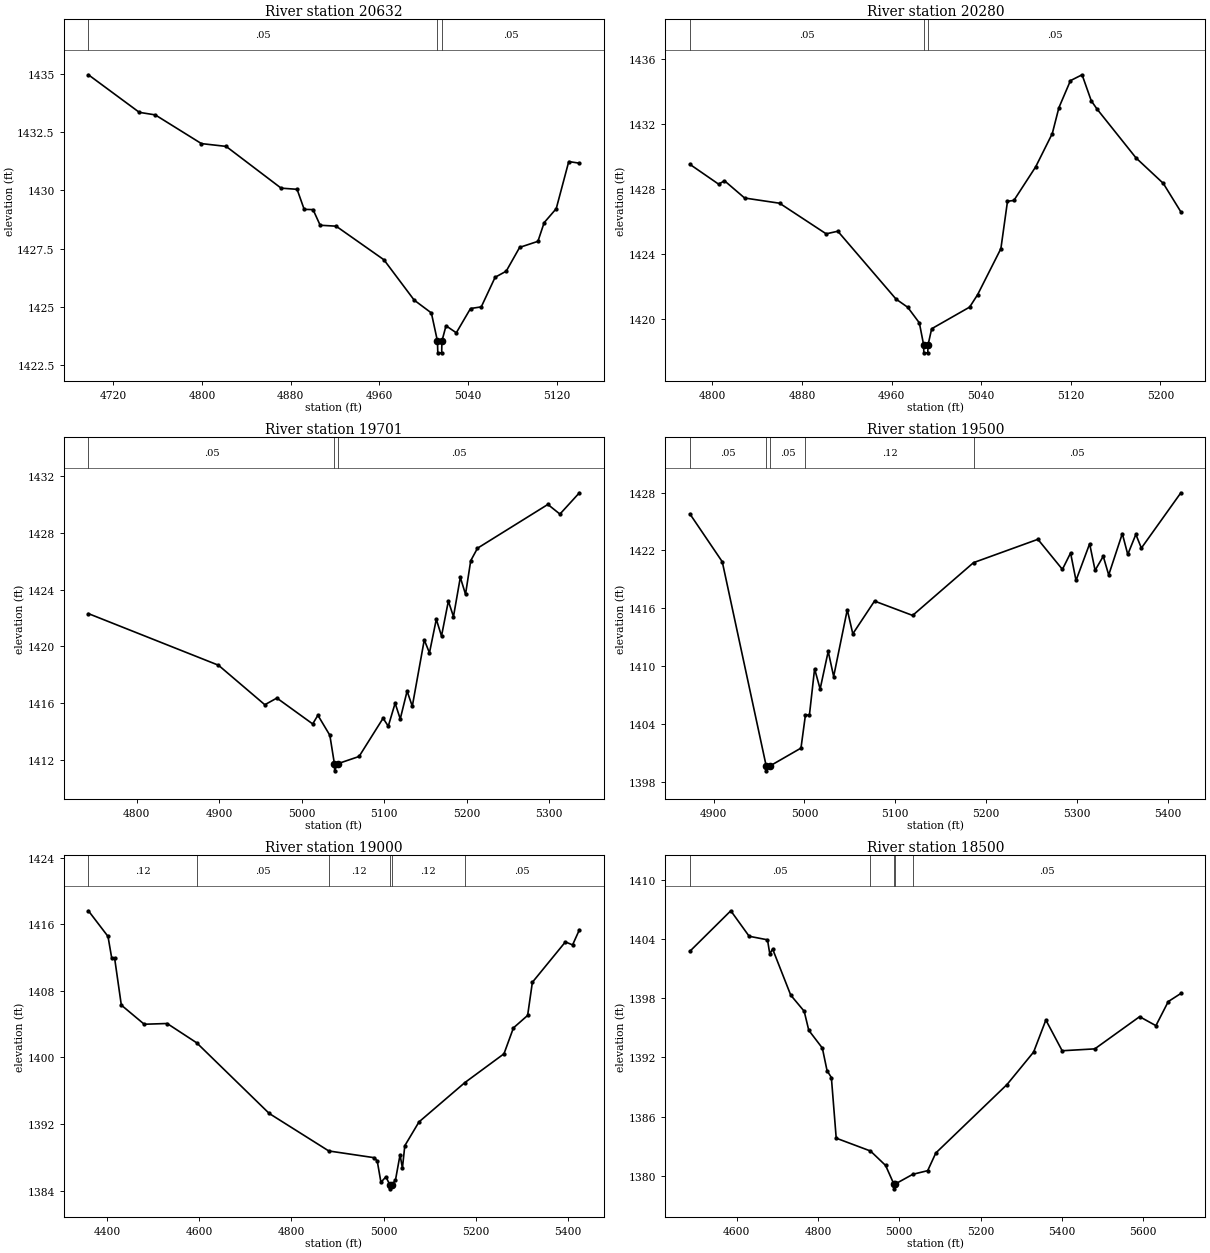
Type RM Length L Ch R = 1,20632,352,352,352
BEGIN DESCRIPTION:
PRAIRIE MT SPRING BRANCH 41.5
END DESCRIPTION:
XS GIS Cut Line= 3
      2760088.22     10180226.60      2760323.16     10180416.99
      2760387.68     10180541.69
#Sta/Elev= 30
  4697.6 1434.95  4743.5 1433.34  4757.9 1433.23  4799.5 1432.00  4821.8 1431.88
  4871.4 1430.09  4885.8 1430.04  4892.2 1429.18  4900.2 1429.17  4906.6 1428.50
  4921.0 1428.46  4964.1 1427.02  4991.4 1425.29  5006.9 1424.74  5012.4 1423.53
  5012.7 1423.03  5016.2 1423.03  5016.4 1423.53  5020.1 1424.19  5029.4 1423.89
  5042.2 1424.93  5051.9 1425.00  5064.4 1426.27  5074.4 1426.53  5086.5 1427.55
  5103.0 1427.81  5108.6 1428.61  5119.5 1429.21  5130.8 1431.23  5140.4 1431.16
#Mann=3,-1,0
  4697.6    0.05       0  5012.4    0.03       0  5016.4    0.05       0
Bank Sta=5012.4,5016.4
Exp/Cntr=0.3,0.1

Type RM Length L Ch R = 1,20280,579,579,579
BEGIN DESCRIPTION:
PRAIRIE MT SPRING BRANCH 41.0
END DESCRIPTION:
XS GIS Cut Line= 3
      2759958.61     10180660.30      2760233.06     10180738.37
      2760380.89     10180778.04
#Sta/Elev= 30
  4779.9 1429.51  4805.6 1428.29  4810.8 1428.50  4828.8 1427.44  4860.0 1427.12
  4901.6 1425.24  4912.0 1425.40  4964.0 1421.23  4974.4 1420.73  4984.8 1419.77
  4988.6 1418.43  4988.8 1417.93  4992.3 1417.93  4992.6 1418.43  4995.8 1419.41
  5029.7 1420.74  5036.8 1421.50  5057.6 1424.33  5063.5 1427.24  5069.2 1427.29
  5088.7 1429.36  5103.5 1431.40  5109.4 1432.99  5119.7 1434.65  5130.1 1435.01
  5138.3 1433.41  5143.5 1432.90  5178.3 1429.90  5202.6 1428.34  5218.3 1426.59
#Mann=3,-1,0
  4779.9    0.05       0  4988.6    0.05       0  4992.6    0.05       0
Bank Sta=4988.6,4992.6
Exp/Cntr=0.3,0.1

Type RM Length L Ch R = 1,19701,201,201,201
BEGIN DESCRIPTION:
PRAIRIE MT SPRING BRANCH 40.0
END DESCRIPTION:
XS GIS Cut Line= 3
      2759716.67     10181081.61      2759922.50     10181238.00
      2760190.65     10181034.71
#Sta/Elev= 30
  4741.5 1422.31  4899.1 1418.68  4955.3 1415.90  4969.9 1416.37  5013.3 1414.55
  5019.6 1415.16  5034.1 1413.75  5039.6 1411.75  5039.9 1411.25  5043.6 1411.75
  5069.5 1412.26  5098.6 1414.95  5104.9 1414.39  5113.2 1416.01  5119.4 1414.90
  5127.7 1416.86  5134.0 1415.79  5148.5 1420.46  5154.8 1419.55  5163.1 1421.91
  5169.4 1420.73  5177.7 1423.19  5183.9 1422.10  5192.2 1424.86  5198.5 1423.67
  5204.8 1426.03  5213.0 1426.91  5298.3 1429.99  5312.9 1429.31  5336.5 1430.81
#Mann=3,-1,0
  4741.5    0.05       0  5039.6    0.03       0  5043.6    0.05       0
Bank Sta=5039.6,5043.6
Exp/Cntr=0.3,0.1

Type RM Length L Ch R = 1,19500,500,500,500
BEGIN DESCRIPTION:
PRAIRIE MT SPRING BRANCH 39.0
END DESCRIPTION:
XS GIS Cut Line= 3
      2759955.68     10181503.12      2760024.23     10181397.16
      2760255.71     10181053.08
#Sta/Elev= 30
  4873.8 1425.79  4909.5 1420.82  4957.9 1399.62  4958.1 1399.12  4961.9 1399.62
  4996.2 1401.48  5001.1 1404.91  5005.5 1404.91  5011.2 1409.71  5017.3 1407.61
  5026.2 1411.52  5032.2 1408.91  5047.2 1415.84  5053.3 1413.34  5077.2 1416.74
  5119.2 1415.25  5186.3 1420.73  5257.2 1423.15  5284.2 1420.03  5293.2 1421.73
  5299.2 1418.88  5314.2 1422.69  5320.2 1419.93  5329.2 1421.39  5335.2 1419.45
  5350.2 1423.74  5356.2 1421.58  5365.1 1423.66  5371.2 1422.24  5414.7 1427.98
#Mann=5,-1,0
  4873.8    0.05       0  4957.9    0.05       0  4961.9    0.05       0
  5001.1    0.12       0  5186.3    0.05       0
Bank Sta=4957.9,4961.9
Exp/Cntr=0.3,0.1

Type RM Length L Ch R = 1,19000,500,500,500
BEGIN DESCRIPTION:
PRAIRIE MT SPRING BRANCH 38.0
END DESCRIPTION:
XS GIS Cut Line= 3
      2760005.72     10181803.09      2760509.54     10181408.26
      2760417.52     10180993.44
#Sta/Elev= 30
  4359.9 1417.62  4402.4 1414.54  4410.5 1411.93  4416.8 1411.91  4431.3 1406.29
  4481.0 1403.99  4530.7 1404.08  4594.8 1401.76  4752.2 1393.27  4881.3 1388.77
  4980.0 1387.96  4986.4 1387.57  4994.4 1385.01  5005.3 1385.66  5013.5 1384.72
  5013.8 1384.22  5017.5 1384.72  5025.8 1385.23  5035.9 1388.31  5041.0 1386.71
  5046.2 1389.40  5077.0 1392.26  5176.4 1396.98  5261.3 1400.44  5281.8 1403.55
  5312.6 1405.05  5322.9 1409.03  5394.5 1413.88  5410.1 1413.52  5424.9 1415.34
#Mann=6,-1,0
  4359.9    0.12       0  4594.8    0.05       0  4881.3    0.12       0
  5013.5    0.07       0  5017.5    0.12       0  5176.4    0.05       0
Bank Sta=5013.5,5017.5
Exp/Cntr=0.3,0.1

Type RM Length L Ch R = 1,18500,500,500,500
BEGIN DESCRIPTION:
PRAIRIE MT SPRING BRANCH 37.0
END DESCRIPTION:
XS GIS Cut Line= 3
      2760495.63     10182256.44      2760720.44     10181792.77
      2760773.42     10181101.89
#Sta/Elev= 30
  4484.7 1402.74  4585.4 1406.84  4630.6 1404.26  4675.7 1403.90  4681.3 1402.49
  4688.4 1402.96  4732.9 1398.30  4766.0 1396.67  4777.3 1394.74  4810.7 1392.94
  4822.3 1390.65  4832.9 1389.96  4844.8 1383.82  4929.1 1382.52  4966.3 1381.06
  4986.5 1379.19  4986.8 1378.69  4990.5 1379.19  5033.2 1380.16  5069.9 1380.53
  5089.9 1382.32  5265.1 1389.25  5330.6 1392.54  5360.7 1395.78  5400.8 1392.67
  5481.1 1392.86  5591.4 1396.12  5631.5 1395.21  5661.9 1397.65  5692.9 1398.47
#Mann=5,-1,0
  4484.7    0.05       0  4929.1    0.12       0  4986.5    0.07       0
  4990.5    0.12       0  5033.2    0.05       0
Bank Sta=4986.5,4990.5
Exp/Cntr=0.3,0.1

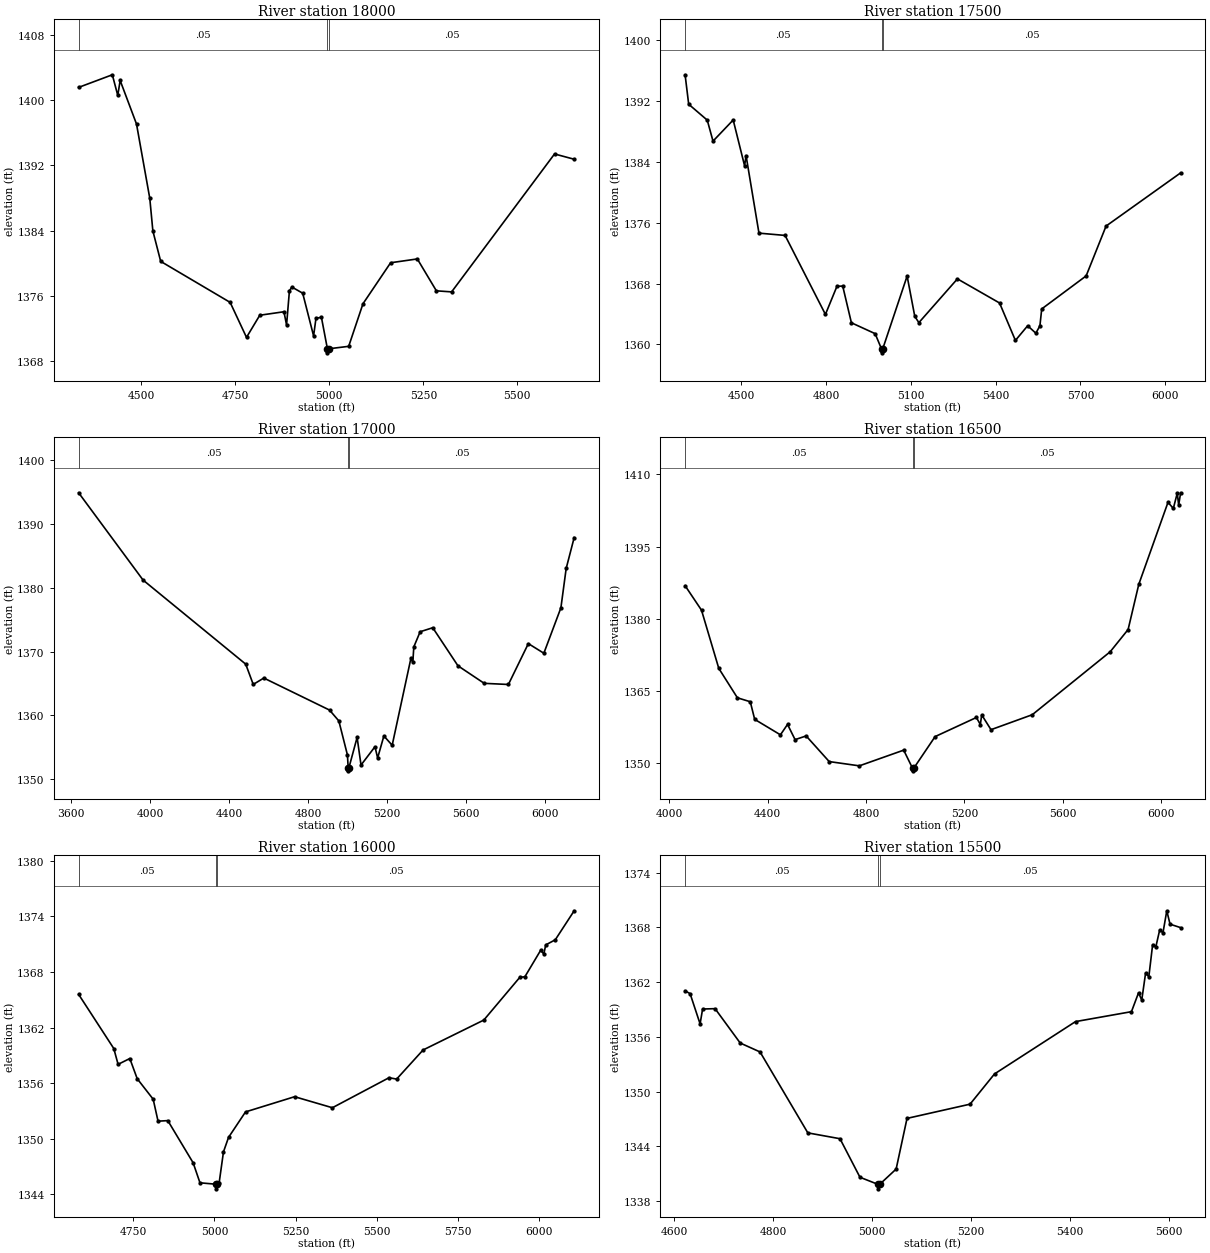
Type RM Length L Ch R = 1,18000,500,500,500
BEGIN DESCRIPTION:
PRAIRIE MT SPRING BRANCH 36.0
END DESCRIPTION:
XS GIS Cut Line= 3
      2760608.46     10182351.93      2761135.61     10181943.92
      2761242.16     10181301.60
#Sta/Elev= 30
  4333.4 1401.59  4423.0 1403.14  4437.5 1400.60  4443.8 1402.44  4487.3 1397.09
  4522.6 1387.96  4530.8 1383.95  4551.6 1380.21  4736.3 1375.17  4779.8 1370.87
  4815.1 1373.59  4879.4 1374.02  4886.3 1372.39  4893.9 1376.58  4900.2 1377.06
  4929.2 1376.30  4958.2 1371.05  4964.5 1373.21  4979.0 1373.34  4994.9 1369.47
  4995.1 1368.97  4998.9 1369.47  5051.5 1369.77  5089.5 1375.00  5163.0 1380.04
  5234.0 1380.51  5284.7 1376.59  5325.2 1376.46  5598.9 1393.41  5651.1 1392.76
#Mann=3,-1,0
  4333.4    0.05       0  4994.9    0.05       0  4998.9    0.05       0
Bank Sta=4994.9,4998.9
Exp/Cntr=0.3,0.1

Type RM Length L Ch R = 1,17500,500,500,500
BEGIN DESCRIPTION:
PRAIRIE MT SPRING BRANCH 35.0
END DESCRIPTION:
XS GIS Cut Line= 3
      2760618.88     10182520.75      2761303.84     10182382.39
      2761955.69     10181553.11
#Sta/Elev= 30
  4301.2 1395.44  4313.9 1391.57  4379.6 1389.48  4400.0 1386.72  4471.4 1389.50
  4511.8 1383.47  4516.9 1384.83  4562.6 1374.63  4655.0 1374.33  4797.8 1363.95
  4838.6 1367.65  4859.0 1367.67  4889.7 1362.85  4973.7 1361.42  4996.4 1359.40
  4996.6 1358.90  5000.4 1359.40  5086.9 1368.99  5114.0 1363.69  5128.5 1362.87
  5264.9 1368.62  5414.0 1365.45  5470.1 1360.53  5513.5 1362.46  5542.4 1361.48
  5556.8 1362.45  5563.2 1364.67  5720.4 1369.01  5790.9 1375.56  6054.8 1382.55
#Mann=3,-1,0
  4301.2    0.05       0  4996.4    0.05       0  5000.4    0.05       0
Bank Sta=4996.4,5000.4
Exp/Cntr=0.3,0.1

Type RM Length L Ch R = 1,17000,500,500,500
BEGIN DESCRIPTION:
PRAIRIE MT SPRING BRANCH 34.0
END DESCRIPTION:
XS GIS Cut Line= 3
      2760431.36     10183083.26      2761700.39     10182592.00
      2762791.59     10182236.32
#Sta/Elev= 30
  3639.2 1394.92  3965.5 1381.23  4485.0 1368.05  4523.1 1364.87  4576.7 1365.87
  4909.2 1360.85  4956.4 1359.15  5000.0 1353.80  5003.6 1351.82  5003.8 1351.32
  5007.6 1351.82  5048.9 1356.56  5068.7 1352.23  5139.3 1355.10  5152.8 1353.34
  5184.4 1356.79  5226.4 1355.33  5321.1 1368.94  5330.8 1368.33  5336.0 1370.76
  5368.0 1373.13  5431.8 1373.76  5559.4 1367.79  5692.3 1365.04  5814.7 1364.86
  5915.7 1371.27  5994.2 1369.76  6080.5 1376.88  6107.2 1383.05  6147.7 1387.90
#Mann=3,-1,0
  3639.2    0.05       0  5003.6    0.05       0  5007.6    0.05       0
Bank Sta=5003.6,5007.6
Exp/Cntr=0.3,0.1

Type RM Length L Ch R = 1,16500,500,500,500
BEGIN DESCRIPTION:
PRAIRIE MT SPRING BRANCH 33.0
END DESCRIPTION:
XS GIS Cut Line= 3
      2761055.69     10183403.11      2761913.67     10183029.24
      2762855.70     10182503.10
#Sta/Elev= 30
  4064.1 1386.84  4130.8 1381.74  4201.1 1369.62  4276.8 1363.49  4329.1 1362.67
  4347.1 1359.00  4451.7 1355.78  4480.6 1357.95  4511.3 1354.78  4556.3 1355.55
  4650.0 1350.21  4772.6 1349.32  4952.9 1352.59  4989.3 1348.78  4989.5 1348.28
  4993.3 1348.78  5080.6 1355.41  5248.5 1359.39  5264.5 1357.93  5270.2 1359.93
  5307.9 1356.85  5475.8 1359.97  5792.6 1373.08  5865.4 1377.71  5908.8 1387.12
  6027.6 1404.20  6049.3 1402.93  6065.3 1406.11  6071.0 1403.63  6079.0 1406.19
#Mann=3,-1,0
  4064.1    0.05       0  4989.3    0.03       0  4993.3    0.05       0
Bank Sta=4989.3,4993.3
Exp/Cntr=0.3,0.1

Type RM Length L Ch R = 1,16000,500,500,500
BEGIN DESCRIPTION:
PRAIRIE MT SPRING BRANCH 32.0
END DESCRIPTION:
XS GIS Cut Line= 3
      2761405.67     10183603.12      2761753.59     10183370.36
      2762705.71     10182803.10
#Sta/Elev= 30
  4581.4 1365.59  4689.7 1359.75  4703.0 1358.04  4739.1 1358.67  4761.9 1356.49
  4811.1 1354.28  4826.1 1351.91  4856.2 1351.97  4934.2 1347.42  4955.3 1345.26
  5004.3 1345.11  5004.6 1344.61  5008.3 1345.11  5014.1 1345.19  5027.7 1348.60
  5043.3 1350.16  5095.6 1352.91  5246.9 1354.55  5363.3 1353.36  5537.9 1356.60
  5561.2 1356.45  5642.7 1359.59  5829.9 1362.82  5940.8 1367.43  5956.4 1367.49
  6005.1 1370.35  6014.8 1369.95  6020.7 1370.93  6050.1 1371.48  6108.3 1374.61
#Mann=3,-1,0
  4581.4    0.05       0  5004.3    0.05       0  5008.3    0.05       0
Bank Sta=5004.3,5008.3
Exp/Cntr=0.3,0.1

Type RM Length L Ch R = 1,15500,500,500,500
BEGIN DESCRIPTION:
PRAIRIE MT SPRING BRANCH 31.0
END DESCRIPTION:
XS GIS Cut Line= 3
      2761555.72     10183753.12      2761930.26     10183806.34
      2762405.69     10183403.11
#Sta/Elev= 30
  4621.7 1361.04  4631.8 1360.74  4652.0 1357.42  4657.1 1359.05  4682.3 1359.09
  4733.1 1355.32  4773.2 1354.34  4869.8 1345.46  4934.8 1344.82  4975.2 1340.59
  5011.2 1339.82  5011.4 1339.32  5015.2 1339.82  5048.3 1341.49  5070.3 1347.05
  5197.7 1348.61  5247.2 1351.93  5410.9 1357.67  5524.0 1358.76  5538.3 1360.83
  5544.8 1360.03  5552.6 1363.01  5559.1 1362.59  5566.8 1366.12  5573.4 1365.90
  5581.1 1367.74  5587.7 1367.42  5595.4 1369.83  5602.0 1368.36  5623.4 1367.98
#Mann=3,-1,0
  4621.7    0.05       0  5011.2    0.03       0  5015.2    0.05       0
Bank Sta=5011.2,5015.2
Exp/Cntr=0.3,0.1

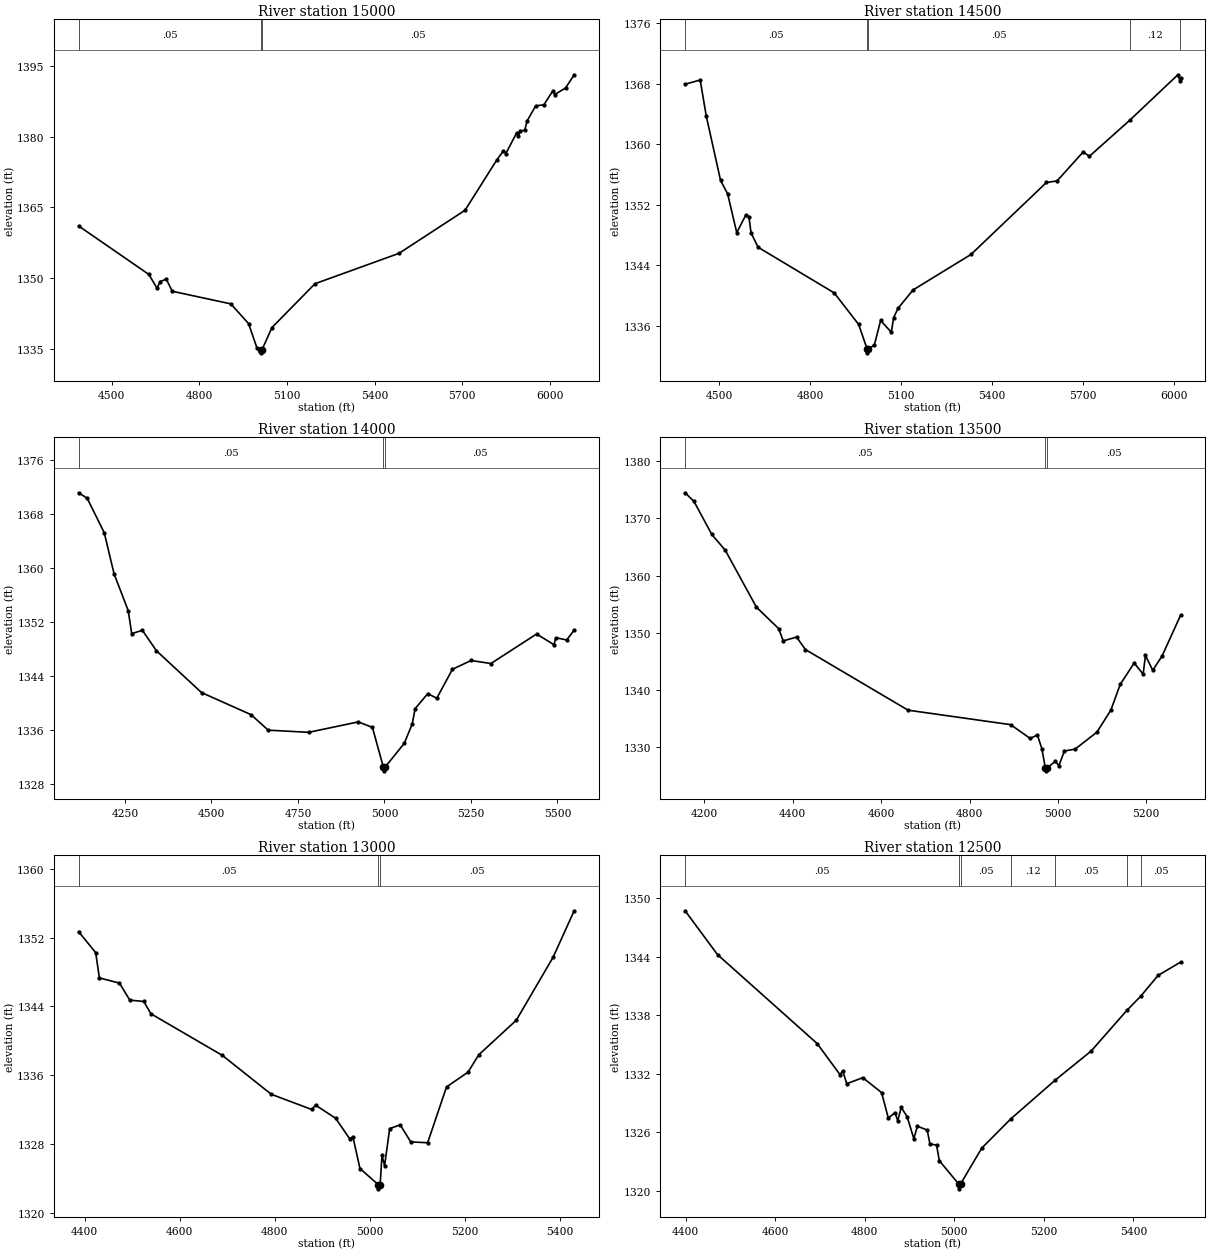
Type RM Length L Ch R = 1,15000,500,500,500
BEGIN DESCRIPTION:
PRAIRIE MT SPRING BRANCH 30.0
END DESCRIPTION:
XS GIS Cut Line= 3
      2761528.58     10184416.59      2762115.40     10184240.74
      2763055.65     10183703.13
#Sta/Elev= 30
  4387.4 1361.07  4627.8 1350.77  4655.7 1347.84  4666.2 1349.25  4687.1 1349.78
  4708.0 1347.20  4908.1 1344.52  4969.0 1340.33  4997.5 1335.16  5009.9 1334.62
  5010.1 1334.12  5013.9 1334.62  5048.9 1339.49  5196.2 1348.80  5483.6 1355.25
  5709.6 1364.40  5818.2 1375.08  5841.2 1377.04  5849.2 1376.44  5886.6 1380.88
  5892.4 1380.17  5898.8 1381.27  5914.0 1381.39  5921.9 1383.36  5951.4 1386.58
  5979.5 1386.80  6010.4 1389.79  6016.2 1388.98  6053.6 1390.37  6083.1 1393.18
#Mann=3,-1,0
  4387.4    0.05       0  5009.9    0.05       0  5013.9    0.05       0
Bank Sta=5009.9,5013.9
Exp/Cntr=0.3,0.1

Type RM Length L Ch R = 1,14500,500,500,500
BEGIN DESCRIPTION:
PRAIRIE MT SPRING BRANCH 29.0
END DESCRIPTION:
XS GIS Cut Line= 3
      2761716.15     10184749.90      2762324.93     10184689.21
      2763111.29     10184035.18
#Sta/Elev= 30
  4388.2 1367.95  4438.0 1368.51  4458.1 1363.73  4505.2 1355.23  4528.4 1353.47
  4558.6 1348.33  4588.7 1350.68  4598.8 1350.39  4605.8 1348.30  4628.9 1346.40
  4880.2 1340.36  4960.6 1336.20  4988.7 1332.94  4989.0 1332.44  4992.7 1332.94
  5012.4 1333.47  5033.2 1336.72  5068.4 1335.16  5076.2 1337.10  5090.5 1338.32
  5140.0 1340.75  5331.4 1345.45  5580.1 1354.96  5615.2 1355.17  5701.1 1358.99
  5722.0 1358.43  5855.0 1363.19  6013.6 1369.20  6020.0 1368.44  6022.8 1368.77
#Mann=5,-1,0
  4388.2    0.05       0  4988.7    0.05       0  4992.7    0.05       0
  5855.0    0.12       0  6020.0    0.05       0
Bank Sta=4988.7,4992.7
Exp/Cntr=0.3,0.1

Type RM Length L Ch R = 1,14000,500,500,500
BEGIN DESCRIPTION:
PRAIRIE MT SPRING BRANCH 28.0
END DESCRIPTION:
XS GIS Cut Line= 3
      2761805.70     10185203.11      2762669.65     10185017.77
      2763188.39     10184840.17
#Sta/Elev= 30
  4116.4 1371.15  4141.1 1370.34  4190.5 1365.23  4218.7 1359.17  4259.6 1353.72
  4269.8 1350.30  4300.5 1350.80  4341.4 1347.76  4471.6 1341.58  4614.7 1338.31
  4664.1 1336.02  4781.2 1335.70  4924.4 1337.24  4965.3 1336.43  4997.2 1330.50
  4997.4 1330.00  5001.2 1330.50  5057.3 1334.07  5080.4 1336.94  5088.6 1339.19
  5125.2 1341.43  5151.2 1340.74  5196.6 1345.03  5250.4 1346.33  5307.6 1345.88
  5439.7 1350.25  5490.1 1348.66  5495.4 1349.70  5526.7 1349.37  5548.3 1350.82
#Mann=3,-1,0
  4116.4    0.05       0  4997.2    0.05       0  5001.2    0.05       0
Bank Sta=4997.2,5001.2
Exp/Cntr=0.3,0.1

Type RM Length L Ch R = 1,13500,500,500,500
BEGIN DESCRIPTION:
PRAIRIE MT SPRING BRANCH 27.0
END DESCRIPTION:
XS GIS Cut Line= 3
      2761755.72     10185303.12      2762591.74     10185416.70
      2762855.66     10185503.10
#Sta/Elev= 30
  4156.3 1374.49  4176.4 1372.98  4216.8 1367.20  4247.1 1364.46  4317.7 1354.50
  4368.2 1350.74  4378.3 1348.61  4408.6 1349.27  4428.7 1347.09  4660.9 1336.50
  4893.0 1333.97  4937.3 1331.56  4953.5 1332.17  4963.6 1329.77  4971.6 1326.40
  4971.9 1325.90  4975.8 1326.40  4993.9 1327.55  5002.3 1326.83  5014.7 1329.37
  5038.8 1329.69  5088.3 1332.66  5119.9 1336.53  5140.9 1340.99  5172.5 1344.74
  5192.8 1342.80  5198.1 1346.06  5214.6 1343.47  5235.6 1345.96  5277.7 1353.11
#Mann=3,-1,0
  4156.3    0.05       0  4971.6    0.05       0  4975.8    0.05       0
Bank Sta=4971.6,4975.8
Exp/Cntr=0.3,0.1

Type RM Length L Ch R = 1,13000,500,500,500
BEGIN DESCRIPTION:
PRAIRIE MT SPRING BRANCH 26.0
END DESCRIPTION:
XS GIS Cut Line= 3
      2761955.68     10185453.11      2762467.95     10185789.43
      2762855.71     10185603.10
#Sta/Elev= 30
  4387.2 1352.69  4423.1 1350.25  4430.9 1347.31  4473.1 1346.71  4494.9 1344.73
  4524.3 1344.57  4539.4 1343.14  4690.0 1338.29  4792.6 1333.78  4877.7 1332.01
  4886.0 1332.51  4928.1 1330.99  4958.3 1328.55  4964.3 1328.86  4979.4 1325.14
  5017.6 1323.28  5017.8 1322.78  5021.8 1323.28  5025.7 1326.68  5031.2 1325.47
  5041.9 1329.79  5064.1 1330.22  5086.2 1328.24  5121.8 1328.14  5161.5 1334.63
  5206.8 1336.35  5229.4 1338.37  5308.4 1342.39  5385.8 1349.71  5430.2 1355.12
#Mann=3,-1,0
  4387.2    0.05       0  5017.6    0.05       0  5021.8    0.05       0
Bank Sta=5017.6,5021.8
Exp/Cntr=0.3,0.1

Type RM Length L Ch R = 1,12500,500,500,500
BEGIN DESCRIPTION:
PRAIRIE MT SPRING BRANCH 25.0
END DESCRIPTION:
XS GIS Cut Line= 3
      2761855.69     10185903.12      2762353.96     10186239.87
      2762855.69     10186303.11
#Sta/Elev= 30
  4398.6 1348.71  4471.0 1344.22  4693.8 1335.10  4744.7 1331.92  4750.7 1332.32
  4759.7 1330.99  4795.6 1331.61  4837.6 1330.08  4852.6 1327.47  4867.6 1328.03
  4873.6 1327.19  4881.4 1328.56  4894.6 1327.62  4909.6 1325.36  4917.6 1326.64
  4939.5 1326.24  4945.5 1324.84  4960.5 1324.69  4966.5 1323.11  5009.7 1320.72
  5010.0 1320.22  5014.0 1320.72  5061.5 1324.40  5126.3 1327.39  5225.3 1331.35
  5305.8 1334.34  5385.7 1338.51  5416.8 1339.97  5455.3 1342.09  5505.7 1343.45
#Mann=7,-1,0
  4398.6    0.05       0  5009.7    0.05       0  5014.0    0.05       0
  5126.3    0.12       0  5225.3    0.05       0  5385.7    0.12       0
  5416.8    0.05       0
Bank Sta=5009.7,5014
Exp/Cntr=0.3,0.1

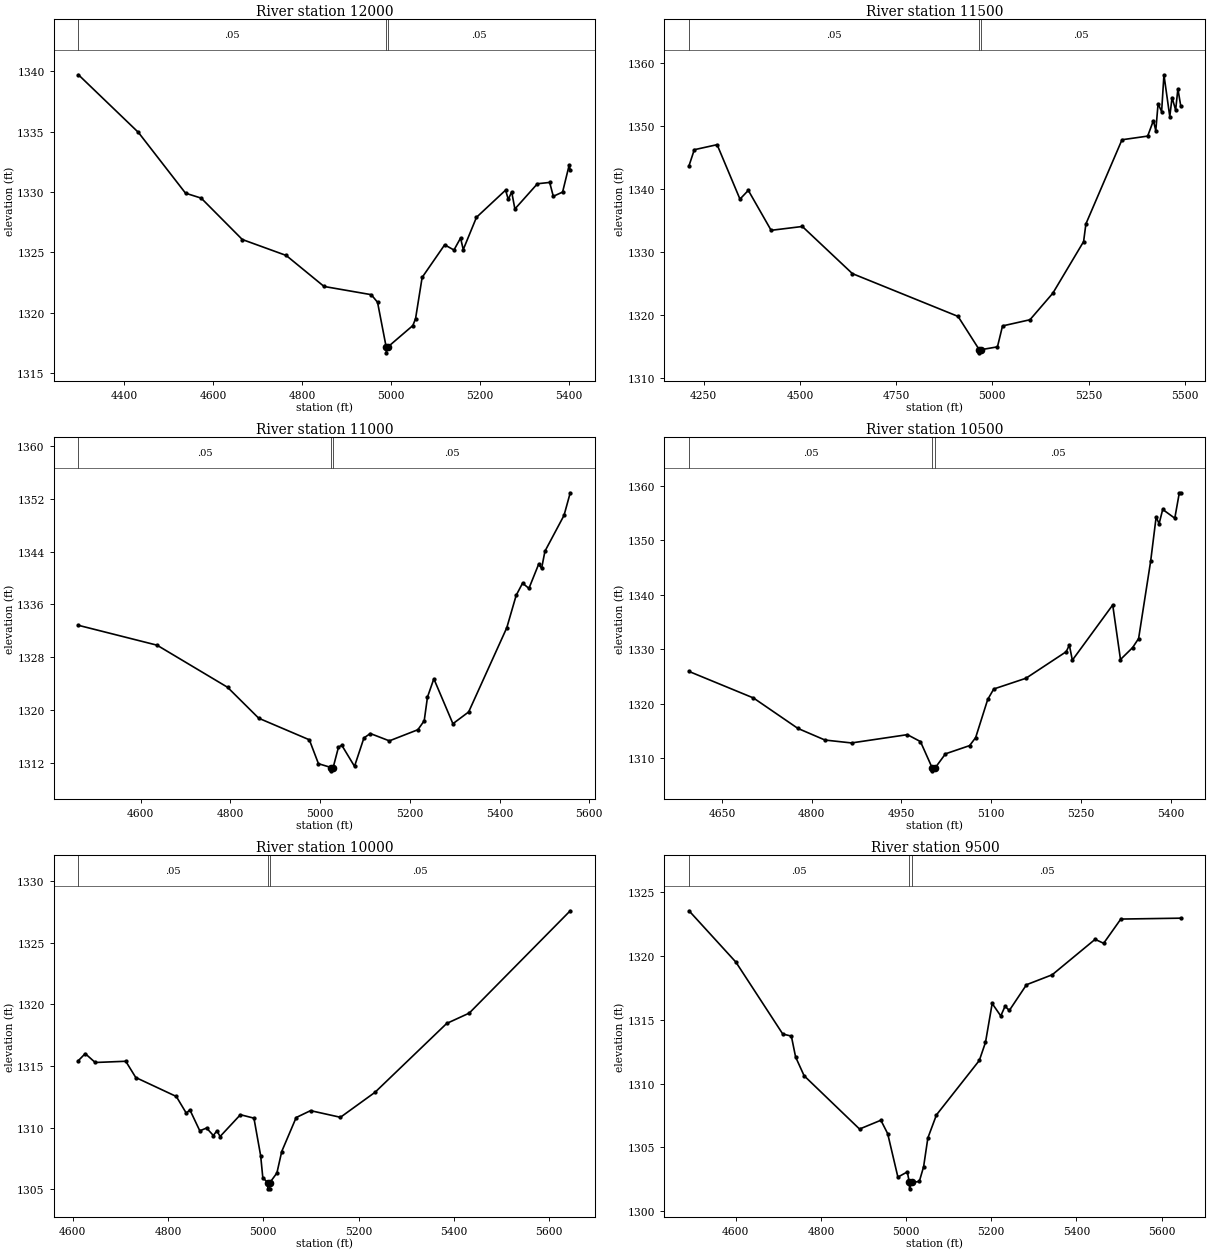
Type RM Length L Ch R = 1,12000,500,500,500
BEGIN DESCRIPTION:
PRAIRIE MT SPRING BRANCH 24.0
END DESCRIPTION:
XS GIS Cut Line= 3
      2761805.70     10186203.13      2762283.41     10186717.80
      2762613.50     10186948.82
#Sta/Elev= 30
  4297.8 1339.70  4432.4 1334.93  4538.4 1329.89  4573.6 1329.48  4666.0 1326.05
  4764.6 1324.73  4849.7 1322.16  4955.7 1321.48  4969.9 1320.85  4989.2 1317.16
  4989.5 1316.66  4993.5 1317.16  5049.2 1318.92  5055.3 1319.49  5070.1 1322.91
  5120.7 1325.61  5141.6 1325.18  5156.4 1326.17  5162.5 1325.22  5192.2 1327.89
  5257.6 1330.14  5263.7 1329.37  5271.3 1330.00  5278.5 1328.58  5329.1 1330.67
  5356.7 1330.78  5364.8 1329.63  5385.7 1329.98  5400.6 1332.23  5402.9 1331.81
#Mann=3,-1,0
  4297.8    0.05       0  4989.2    0.05       0  4993.5    0.05       0
Bank Sta=4989.2,4993.5
Exp/Cntr=0.3,0.1

Type RM Length L Ch R = 1,11500,500,500,500
BEGIN DESCRIPTION:
PRAIRIE MT SPRING BRANCH 23.0
END DESCRIPTION:
XS GIS Cut Line= 3
      2761305.70     10186703.12      2761993.49     10187088.49
      2762405.67     10187353.10
#Sta/Elev= 30
  4211.6 1343.74  4225.3 1346.28  4284.6 1347.08  4344.0 1338.44  4365.7 1339.83
  4425.0 1333.49  4506.1 1334.10  4636.2 1326.62  4910.8 1319.83  4965.9 1314.55
  4966.2 1314.05  4970.3 1314.55  5013.2 1315.00  5026.4 1318.32  5097.7 1319.30
  5157.1 1323.51  5237.1 1331.70  5243.1 1334.51  5336.9 1347.86  5403.6 1348.44
  5418.5 1350.89  5424.7 1349.32  5430.7 1353.57  5439.9 1352.33  5445.9 1358.17
  5461.1 1351.53  5467.0 1354.55  5476.3 1352.57  5482.2 1355.94  5489.8 1353.15
#Mann=3,-1,0
  4211.6    0.05       0  4965.9    0.05       0  4970.3    0.05       0
Bank Sta=4965.9,4970.3
Exp/Cntr=0.3,0.1

Type RM Length L Ch R = 1,11000,500,500,500
BEGIN DESCRIPTION:
PRAIRIE MT SPRING BRANCH 22.0
END DESCRIPTION:
XS GIS Cut Line= 3
      2761305.71     10187253.12      2761797.77     10187473.13
      2762205.70     10187853.12
#Sta/Elev= 30
  4461.0 1332.85  4636.2 1329.85  4793.4 1323.49  4863.0 1318.81  4975.8 1315.55
  4996.1 1311.94  5024.5 1311.36  5024.8 1310.86  5028.9 1311.36  5040.8 1314.45
  5048.2 1314.72  5076.5 1311.54  5097.5 1315.83  5111.7 1316.50  5154.2 1315.39
  5217.7 1317.07  5231.9 1318.42  5239.2 1322.01  5253.4 1324.77  5295.9 1317.98
  5331.0 1319.76  5416.0 1332.48  5437.0 1337.39  5451.2 1339.22  5465.4 1338.43
  5486.9 1342.06  5493.7 1341.48  5501.1 1344.05  5543.6 1349.46  5557.5 1352.88
#Mann=3,-1,0
  4461.0    0.05       0  5024.5    0.05       0  5028.9    0.05       0
Bank Sta=5024.5,5028.9
Exp/Cntr=0.3,0.1

Type RM Length L Ch R = 1,10500,500,500,500
BEGIN DESCRIPTION:
PRAIRIE MT SPRING BRANCH 21.0
END DESCRIPTION:
XS GIS Cut Line= 3
      2761385.37     10187767.25      2761742.25     10187959.14
      2762155.67     10187903.11
#Sta/Elev= 30
  4594.8 1325.89  4702.6 1321.02  4776.8 1315.44  4822.2 1313.30  4866.5 1312.77
  4959.9 1314.29  4981.8 1313.02  5001.6 1308.15  5001.9 1307.65  5006.1 1308.15
  5023.6 1310.77  5064.0 1312.28  5074.1 1313.75  5094.3 1320.76  5104.4 1322.67
  5158.2 1324.64  5225.5 1329.51  5230.8 1330.73  5235.8 1327.96  5303.3 1338.09
  5316.3 1328.08  5336.5 1330.26  5346.6 1331.93  5366.8 1346.17  5375.9 1354.21
  5380.9 1353.02  5386.9 1355.62  5407.1 1354.01  5414.7 1358.68  5417.2 1358.68
#Mann=3,-1,0
  4594.8    0.05       0  5001.6    0.05       0  5006.1    0.05       0
Bank Sta=5001.6,5006.1
Exp/Cntr=0.3,0.1

Type RM Length L Ch R = 1,10000,500,500,500
BEGIN DESCRIPTION:
PRAIRIE MT SPRING BRANCH 20.0
END DESCRIPTION:
XS GIS Cut Line= 3
      2761180.66     10188078.09      2761467.33     10188339.41
      2762105.73     10188253.11
#Sta/Elev= 30
  4612.1 1315.44  4626.3 1316.00  4647.3 1315.28  4711.4 1315.38  4732.4 1314.06
  4817.5 1312.52  4838.5 1311.16  4845.9 1311.44  4866.8 1309.73  4881.0 1309.96
  4895.2 1309.35  4902.6 1309.73  4909.4 1309.27  4952.0 1311.04  4980.4 1310.76
  4994.5 1307.71  4999.0 1305.93  5009.3 1305.52  5009.6 1305.02  5013.5 1305.02
  5013.8 1305.52  5028.6 1306.31  5038.7 1308.05  5069.0 1310.81  5099.2 1311.37
  5161.9 1310.83  5234.5 1312.86  5384.9 1318.45  5432.2 1319.29  5644.2 1327.60
#Mann=3,-1,0
  4612.1    0.05       0  5009.3    0.05       0  5013.8    0.05       0
Bank Sta=5009.3,5013.8
Exp/Cntr=0.3,0.1

Type RM Length L Ch R = 1,9500,500,500,500
BEGIN DESCRIPTION:
PRAIRIE MT SPRING BRANCH 19.0
END DESCRIPTION:
XS GIS Cut Line= 3
      2760855.66     10188753.11      2761364.93     10188780.38
      2762005.68     10188703.11
#Sta/Elev= 30
  4490.0 1323.56  4600.2 1319.53  4710.3 1313.89  4730.4 1313.73  4740.4 1312.09
  4760.4 1310.62  4890.6 1306.44  4940.7 1307.13  4956.7 1306.08  4980.7 1302.67
  5002.9 1303.08  5007.5 1302.25  5008.0 1301.75  5014.1 1302.25  5031.0 1302.33
  5041.1 1303.48  5051.1 1305.74  5071.3 1307.55  5172.0 1311.82  5186.5 1313.24
  5202.2 1316.29  5222.4 1315.31  5232.4 1316.07  5242.5 1315.74  5282.8 1317.76
  5343.2 1318.54  5444.0 1321.32  5464.1 1321.01  5504.4 1322.91  5645.4 1322.98
#Mann=3,-1,0
  4490.0    0.05       0  5007.5    0.05       0  5014.1    0.05       0
Bank Sta=5007.5,5014.1
Exp/Cntr=0.3,0.1