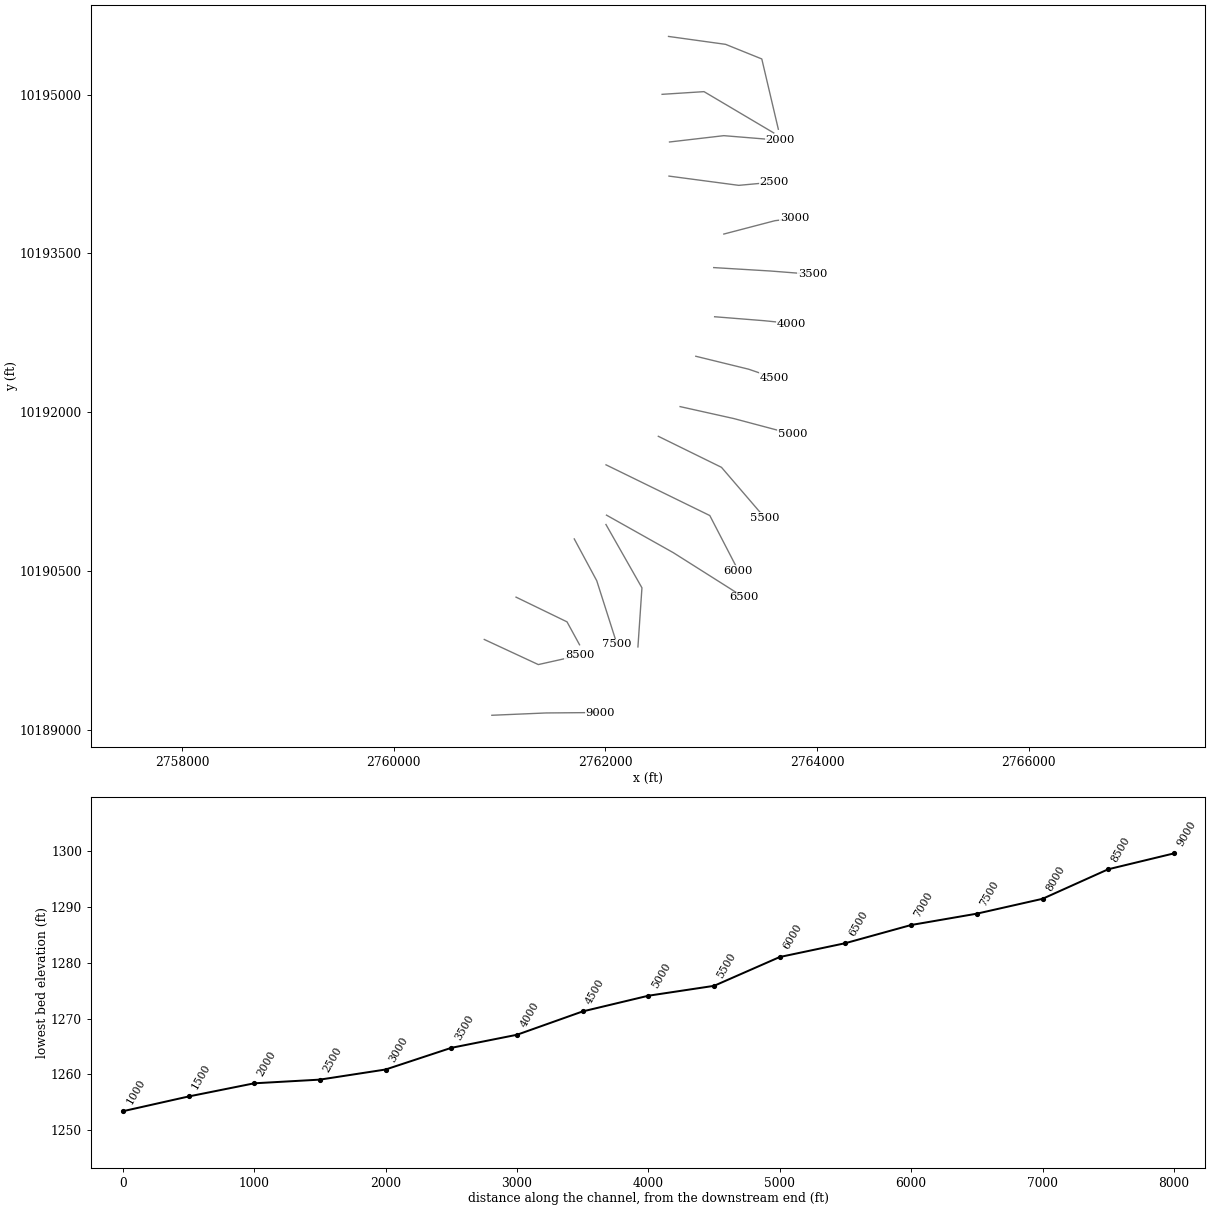
HEC-RAS study PRAIRIE MT SPRING BRANCH.prj: PRAIRIE MT SPRING BRANCH Base Level Engineering

--- PRAIRIE MT SPRING BRANCH.g01 (geometry) --- (continued)

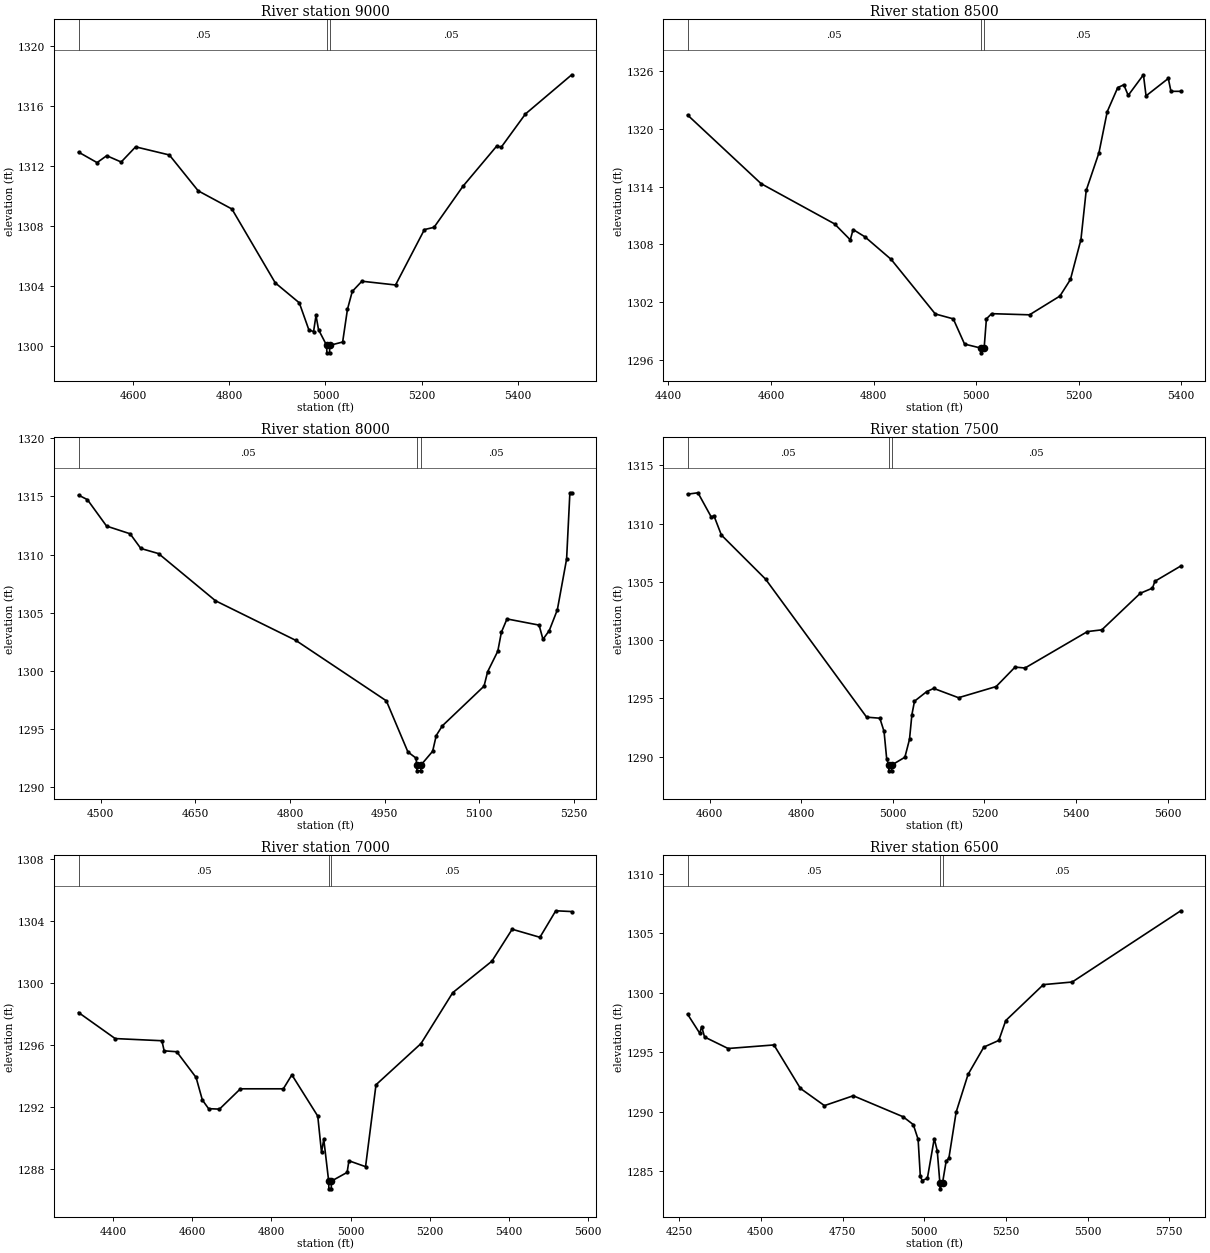
Type RM Length L Ch R = 1,9000,500,500,500
BEGIN DESCRIPTION:
PRAIRIE MT SPRING BRANCH 18.0
END DESCRIPTION:
XS GIS Cut Line= 3
      2760927.10     10189137.06      2761439.83     10189158.96
      2761951.91     10189163.09
#Sta/Elev= 30
  4486.8 1312.93  4525.4 1312.23  4545.4 1312.69  4575.5 1312.27  4605.5 1313.28
  4675.6 1312.74  4735.6 1310.35  4805.7 1309.14  4895.8 1304.22  4945.8 1302.89
  4965.8 1301.08  4975.5 1300.98  4980.5 1302.05  4985.8 1301.10  5002.6 1300.06
  5003.1 1299.56  5008.7 1299.56  5009.2 1300.06  5035.9 1300.28  5045.9 1302.46
  5055.9 1303.65  5075.9 1304.33  5145.9 1304.08  5205.9 1307.77  5225.9 1307.92
  5285.9 1310.65  5355.9 1313.32  5365.9 1313.27  5415.9 1315.47  5512.1 1318.08
#Mann=3,-1,0
  4486.8    0.05       0  5002.6    0.05       0  5009.2    0.05       0
Bank Sta=5002.6,5009.2
Exp/Cntr=0.3,0.1

Type RM Length L Ch R = 1,8500,500,500,500
BEGIN DESCRIPTION:
PRAIRIE MT SPRING BRANCH 17.0
END DESCRIPTION:
XS GIS Cut Line= 3
      2760855.66     10189853.12      2761366.09     10189616.03
      2761755.67     10189703.11
#Sta/Elev= 30
  4437.2 1321.43  4580.6 1314.30  4723.9 1310.12  4754.6 1308.46  4760.1 1309.53
  4783.0 1308.78  4834.3 1306.43  4920.4 1300.76  4955.5 1300.25  4977.5 1297.63
  5008.9 1297.22  5009.4 1296.72  5015.7 1297.22  5020.1 1300.25  5030.3 1300.79
  5104.2 1300.67  5163.5 1302.62  5184.0 1304.34  5204.5 1308.49  5214.8 1313.60
  5239.6 1317.50  5255.8 1321.78  5276.3 1324.28  5288.1 1324.57  5296.7 1323.47
  5326.4 1325.61  5331.5 1323.42  5374.9 1325.23  5380.1 1323.89  5399.2 1323.89
#Mann=3,-1,0
  4437.2    0.05       0  5008.9    0.03       0  5015.7    0.05       0
Bank Sta=5008.9,5015.7
Exp/Cntr=0.3,0.1

Type RM Length L Ch R = 1,8000,500,500,500
BEGIN DESCRIPTION:
PRAIRIE MT SPRING BRANCH 16.0
END DESCRIPTION:
XS GIS Cut Line= 3
      2761155.67     10190253.12      2761637.25     10190019.62
      2761755.69     10189803.10
#Sta/Elev= 30
  4464.8 1315.10  4478.9 1314.71  4509.3 1312.44  4546.6 1311.78  4563.6 1310.52
  4591.7 1310.08  4682.0 1306.03  4809.3 1302.63  4952.9 1297.44  4987.1 1293.05
  5000.0 1292.52  5001.0 1291.93  5001.5 1291.43  5007.3 1291.43  5007.8 1291.93
  5026.3 1293.11  5032.0 1294.46  5041.6 1295.29  5107.8 1298.70  5113.5 1299.94
  5129.6 1301.70  5135.3 1303.33  5144.2 1304.47  5195.1 1303.94  5201.2 1302.72
  5211.2 1303.47  5224.0 1305.25  5238.7 1309.61  5243.9 1315.30  5246.8 1315.30
#Mann=3,-1,0
  4464.8    0.05       0  5001.0    0.05       0  5007.8    0.05       0
Bank Sta=5001,5007.8
Exp/Cntr=0.3,0.1

Type RM Length L Ch R = 1,7500,500,500,500
BEGIN DESCRIPTION:
PRAIRIE MT SPRING BRANCH 15.0
END DESCRIPTION:
XS GIS Cut Line= 3
      2761705.68     10190803.12      2761918.21     10190407.95
      2762109.36     10189808.91
#Sta/Elev= 30
  4551.3 1312.53  4574.0 1312.65  4603.2 1310.56  4608.9 1310.68  4625.2 1309.02
  4721.6 1305.24  4942.5 1293.38  4971.4 1293.29  4980.6 1292.15  4986.3 1289.82
  4990.7 1289.27  4991.2 1288.77  4997.1 1288.77  4997.6 1289.27  5026.1 1289.94
  5036.2 1291.48  5041.4 1293.59  5047.1 1294.75  5073.6 1295.57  5089.0 1295.85
  5143.3 1295.05  5225.5 1296.01  5266.8 1297.68  5288.5 1297.60  5424.9 1300.73
  5456.4 1300.88  5540.4 1304.02  5567.0 1304.46  5572.3 1305.05  5628.8 1306.36
#Mann=3,-1,0
  4551.3    0.05       0  4990.7    0.05       0  4997.6    0.05       0
Bank Sta=4990.7,4997.6
Exp/Cntr=0.3,0.1

Type RM Length L Ch R = 1,7000,500,500,500
BEGIN DESCRIPTION:
PRAIRIE MT SPRING BRANCH 14.0
END DESCRIPTION:
XS GIS Cut Line= 3
      2762005.18     10190939.16      2762345.13     10190341.02
      2762307.27     10189782.90
#Sta/Elev= 30
  4312.0 1298.11  4404.7 1296.43  4522.9 1296.29  4528.6 1295.64  4560.4 1295.58
  4609.4 1293.92  4625.2 1292.47  4641.0 1291.91  4668.5 1291.88  4721.5 1293.19
  4830.0 1293.19  4851.6 1294.09  4917.1 1291.43  4926.6 1289.09  4932.3 1289.94
  4944.7 1287.24  4945.2 1286.74  4951.2 1286.74  4951.7 1287.24  4991.4 1287.80
  4995.9 1288.55  5038.0 1288.17  5064.4 1293.45  5178.3 1296.11  5258.5 1299.39
  5357.5 1301.42  5408.8 1303.48  5479.0 1302.96  5519.1 1304.67  5559.4 1304.62
#Mann=3,-1,0
  4312.0    0.05       0  4944.7    0.03       0  4951.7    0.05       0
Bank Sta=4944.7,4951.7
Exp/Cntr=0.3,0.1

Type RM Length L Ch R = 1,6500,500,500,500
BEGIN DESCRIPTION:
PRAIRIE MT SPRING BRANCH 13.0
END DESCRIPTION:
XS GIS Cut Line= 3
      2762010.35     10191027.71      2762641.90     10190672.89
      2763305.70     10190253.10
#Sta/Elev= 30
  4275.6 1298.20  4313.0 1296.59  4318.7 1297.16  4327.6 1296.28  4399.7 1295.31
  4540.0 1295.61  4621.0 1291.95  4694.6 1290.50  4782.9 1291.33  4935.5 1289.56
  4966.6 1288.90  4981.4 1287.66  4988.2 1284.53  4994.0 1284.19  5009.7 1284.37
  5030.8 1287.72  5040.0 1286.69  5048.0 1283.99  5048.5 1283.49  5056.1 1283.99
  5067.3 1285.83  5075.5 1286.06  5097.8 1289.95  5134.3 1293.13  5182.6 1295.43
  5228.4 1295.99  5249.6 1297.66  5364.9 1300.69  5453.1 1300.91  5785.4 1306.91
#Mann=3,-1,0
  4275.6    0.05       0  5048.0    0.03       0  5056.1    0.05       0
Bank Sta=5048,5056.1
Exp/Cntr=0.3,0.1

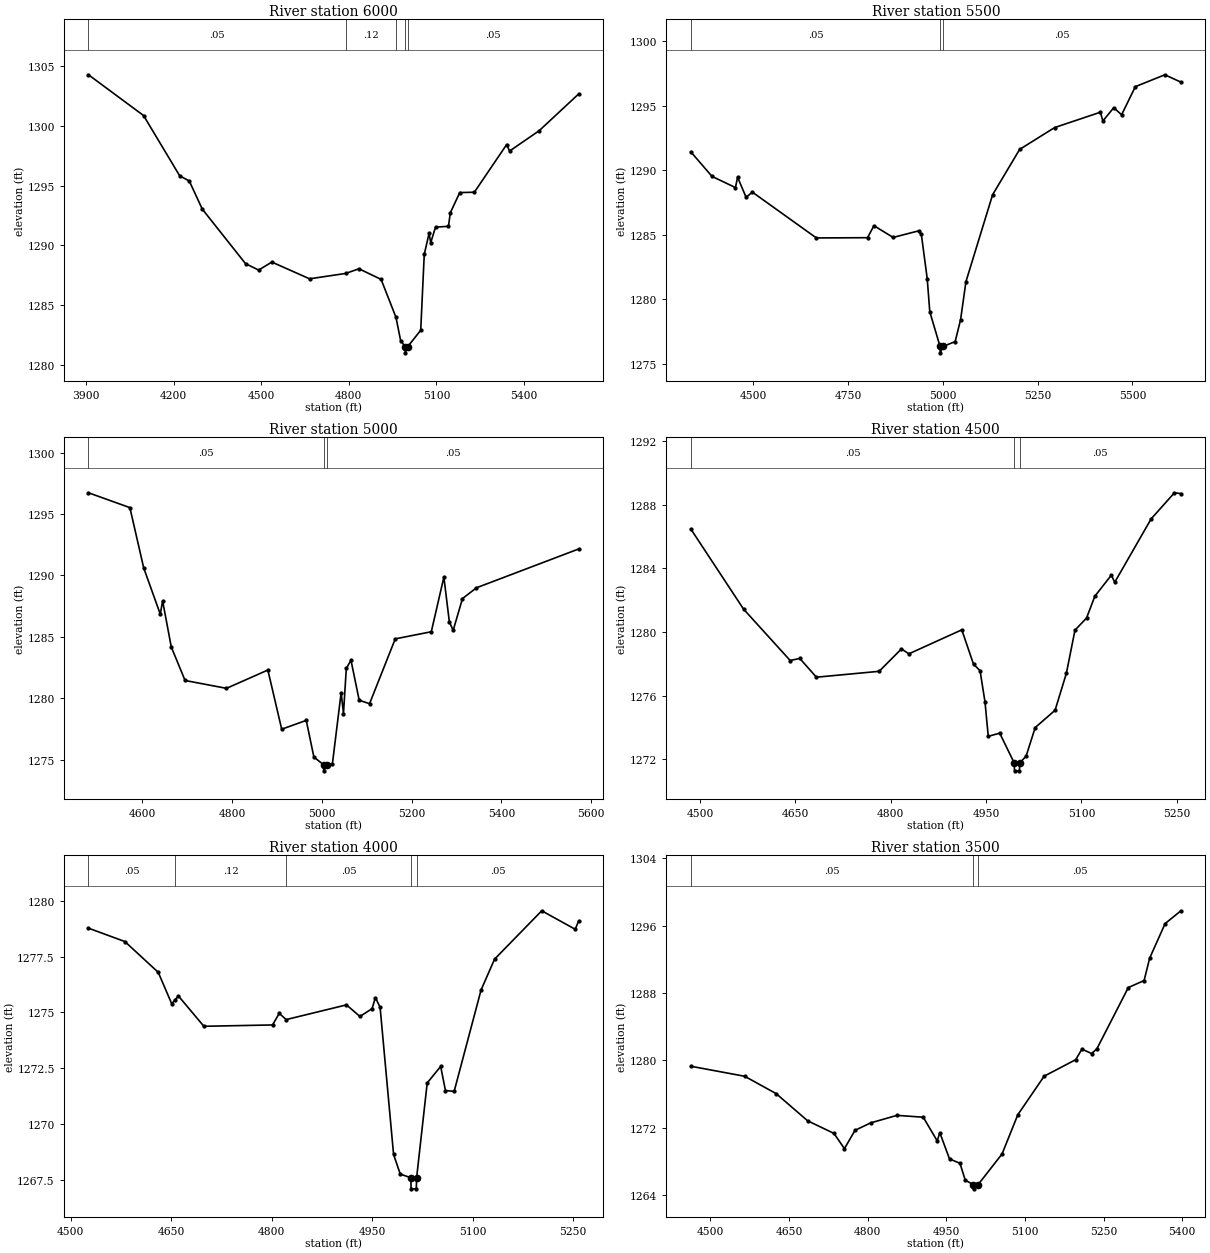
Type RM Length L Ch R = 1,6000,500,500,500
BEGIN DESCRIPTION:
PRAIRIE MT SPRING BRANCH 12.0
END DESCRIPTION:
XS GIS Cut Line= 3
      2762005.72     10191503.10      2762986.20     10191023.94
      2763255.68     10190503.12
#Sta/Elev= 30
  3908.7 1304.26  4097.3 1300.85  4221.0 1295.81  4253.7 1295.38  4298.2 1293.03
  4446.2 1288.47  4491.2 1287.93  4536.3 1288.60  4665.5 1287.20  4789.3 1287.65
  4834.6 1288.04  4910.4 1287.15  4961.3 1283.98  4977.2 1282.04  4992.8 1281.51
  4993.3 1281.01  5001.0 1281.51  5046.0 1282.90  5058.1 1289.24  5074.6 1291.00
  5080.2 1290.22  5096.7 1291.52  5141.0 1291.59  5147.3 1292.72  5179.6 1294.41
  5229.6 1294.44  5340.3 1298.43  5350.0 1297.88  5451.3 1299.58  5586.4 1302.65
#Mann=5,-1,0
  3908.7    0.05       0  4789.3    0.12       0  4961.3    0.05       0
  4992.8    0.03       0  5001.0    0.05       0
Bank Sta=4992.8,5001
Exp/Cntr=0.3,0.1

Type RM Length L Ch R = 1,5500,500,500,500
BEGIN DESCRIPTION:
PRAIRIE MT SPRING BRANCH 11.0
END DESCRIPTION:
XS GIS Cut Line= 3
      2762499.98     10191772.48      2763096.59     10191479.42
      2763505.70     10191003.10
#Sta/Elev= 30
  4335.3 1291.42  4391.2 1289.52  4453.1 1288.65  4458.6 1289.46  4481.1 1287.90
  4497.6 1288.30  4666.5 1284.75  4801.4 1284.77  4818.3 1285.70  4868.9 1284.79
  4936.3 1285.30  4943.3 1285.03  4958.8 1281.60  4965.6 1279.03  4992.6 1276.35
  4993.1 1275.85  5000.8 1276.35  5032.5 1276.72  5046.8 1278.42  5061.0 1281.37
  5131.3 1288.10  5202.6 1291.61  5294.8 1293.30  5415.5 1294.49  5422.1 1293.81
  5450.7 1294.84  5471.5 1294.29  5507.7 1296.47  5585.6 1297.39  5627.9 1296.82
#Mann=3,-1,0
  4335.3    0.05       0  4992.6    0.05       0  5000.8    0.05       0
Bank Sta=4992.6,5000.8
Exp/Cntr=0.3,0.1

Type RM Length L Ch R = 1,5000,500,500,500
BEGIN DESCRIPTION:
PRAIRIE MT SPRING BRANCH 10.0
END DESCRIPTION:
XS GIS Cut Line= 3
      2762705.69     10192053.11      2763212.78     10191940.24
      2763765.58     10191793.32
#Sta/Elev= 30
  4480.5 1296.73  4572.7 1295.52  4603.4 1290.62  4640.4 1286.84  4645.6 1287.92
  4664.9 1284.17  4695.6 1281.44  4787.8 1280.80  4880.0 1282.29  4910.8 1277.47
  4965.5 1278.19  4982.5 1275.20  5004.0 1274.58  5004.5 1274.08  5012.5 1274.58
  5023.7 1274.64  5043.2 1280.45  5048.4 1278.75  5054.7 1282.42  5065.1 1283.09
  5083.4 1279.83  5106.5 1279.55  5163.7 1284.83  5244.0 1285.41  5272.0 1289.86
  5284.2 1286.21  5292.7 1285.52  5313.4 1288.11  5344.5 1288.99  5572.0 1292.15
#Mann=3,-1,0
  4480.5    0.05       0  5004.0    0.03       0  5012.5    0.05       0
Bank Sta=5004,5012.5
Exp/Cntr=0.3,0.1

Type RM Length L Ch R = 1,4500,500,500,500
BEGIN DESCRIPTION:
PRAIRIE MT SPRING BRANCH 9.0
END DESCRIPTION:
XS GIS Cut Line= 3
      2762853.86     10192528.81      2763353.39     10192406.46
      2763596.04     10192323.30
#Sta/Elev= 30
  4485.7 1286.48  4568.7 1281.44  4642.0 1278.21  4657.1 1278.34  4683.2 1277.16
  4781.9 1277.53  4817.0 1278.94  4828.7 1278.63  4911.9 1280.14  4930.3 1277.98
  4940.6 1277.57  4948.4 1275.60  4953.5 1273.44  4971.5 1273.64  4994.3 1271.77
  4994.8 1271.27  5002.5 1271.27  5003.0 1271.77  5013.0 1272.19  5027.3 1273.99
  5058.6 1275.08  5076.4 1277.41  5089.9 1280.12  5108.1 1280.88  5121.1 1282.25
  5147.1 1283.58  5152.4 1283.13  5209.7 1287.12  5246.3 1288.76  5256.5 1288.71
#Mann=3,-1,0
  4485.7    0.05       0  4994.3    0.05       0  5003.0    0.05       0
Bank Sta=4994.3,5003
Exp/Cntr=0.3,0.1

Type RM Length L Ch R = 1,4000,500,500,500
BEGIN DESCRIPTION:
PRAIRIE MT SPRING BRANCH 8.0
END DESCRIPTION:
XS GIS Cut Line= 3
      2763031.87     10192902.06      2763503.57     10192864.37
      2763760.43     10192838.09
#Sta/Elev= 30
  4526.8 1278.78  4581.1 1278.18  4630.9 1276.80  4651.0 1275.39  4655.6 1275.55
  4661.0 1275.74  4699.0 1274.38  4801.5 1274.44  4811.5 1274.96  4821.8 1274.68
  4911.8 1275.34  4931.9 1274.82  4950.0 1275.17  4955.0 1275.67  4962.0 1275.23
  4982.1 1268.63  4992.1 1267.75  5007.8 1267.59  5008.3 1267.09  5016.0 1267.09
  5016.5 1267.59  5032.3 1271.84  5052.4 1272.58  5059.5 1271.50  5072.5 1271.46
  5112.7 1276.01  5132.8 1277.39  5203.2 1279.56  5253.2 1278.73  5258.2 1279.10
#Mann=5,-1,0
  4526.8    0.05       0  4655.6    0.12       0  4821.8    0.05       0
  5007.8    0.05       0  5016.5    0.05       0
Bank Sta=5007.8,5016.5
Exp/Cntr=0.3,0.1

Type RM Length L Ch R = 1,3500,500,500,500
BEGIN DESCRIPTION:
PRAIRIE MT SPRING BRANCH 7.0
END DESCRIPTION:
XS GIS Cut Line= 3
      2763023.20     10193366.47      2763559.53     10193334.15
      2763955.71     10193303.11
#Sta/Elev= 30
  4462.7 1279.30  4565.4 1278.11  4625.5 1276.05  4685.6 1272.82  4735.7 1271.33
  4755.7 1269.52  4775.8 1271.69  4805.8 1272.58  4855.9 1273.47  4906.0 1273.25
  4932.6 1270.44  4937.6 1271.41  4956.1 1268.30  4976.1 1267.78  4986.1 1265.77
  5001.8 1265.25  5002.3 1264.75  5010.6 1265.25  5056.3 1268.89  5086.4 1273.55
  5136.6 1278.12  5196.8 1280.08  5208.6 1281.33  5226.9 1280.81  5236.9 1281.34
  5297.1 1288.64  5327.2 1289.47  5337.8 1292.13  5367.3 1296.23  5397.4 1297.75
#Mann=3,-1,0
  4462.7    0.05       0  5001.8    0.05       0  5010.6    0.05       0
Bank Sta=5001.8,5010.6
Exp/Cntr=0.3,0.1

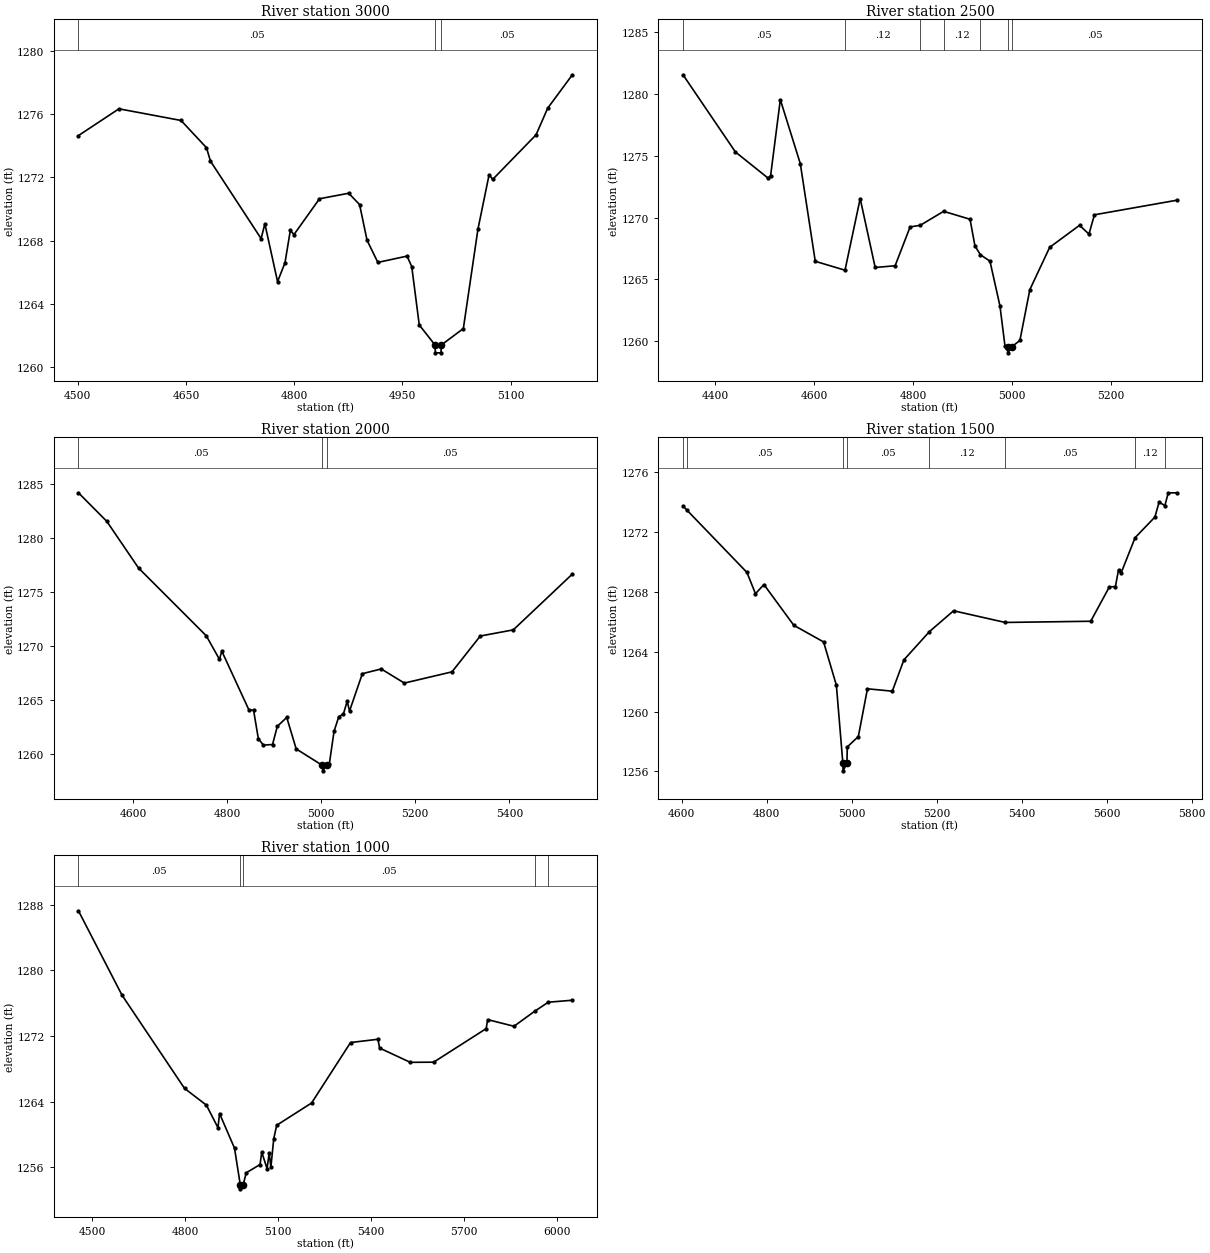
Type RM Length L Ch R = 1,3000,500,500,500
BEGIN DESCRIPTION:
PRAIRIE MT SPRING BRANCH 6.0
END DESCRIPTION:
XS GIS Cut Line= 3
      2763118.65     10193683.31      2763601.44     10193809.47
      2763785.65     10193832.17
#Sta/Elev= 30
  4501.0 1274.66  4557.2 1276.36  4643.2 1275.62  4678.5 1273.89  4684.0 1273.04
  4754.2 1268.12  4759.4 1269.06  4777.0 1265.39  4787.3 1266.59  4794.7 1268.64
  4799.8 1268.38  4835.1 1270.65  4875.6 1271.00  4890.7 1270.28  4901.0 1268.02
  4916.0 1266.61  4956.5 1267.01  4963.0 1266.34  4973.4 1262.64  4995.2 1261.37
  4995.7 1260.87  5003.5 1260.87  5004.0 1261.37  5034.5 1262.41  5054.7 1268.71
  5070.2 1272.18  5075.2 1271.88  5135.3 1274.71  5151.4 1276.40  5185.6 1278.52
#Mann=3,-1,0
  4501.0    0.05       0  4995.2    0.05       0  5004.0    0.05       0
Bank Sta=4995.2,5004
Exp/Cntr=0.3,0.1

Type RM Length L Ch R = 1,2500,500,500,500
BEGIN DESCRIPTION:
PRAIRIE MT SPRING BRANCH 5.0
END DESCRIPTION:
XS GIS Cut Line= 3
      2762600.66     10194230.81      2763259.79     10194143.41
      2763591.77     10194174.10
#Sta/Elev= 30
  4335.1 1281.54  4441.0 1275.30  4507.2 1273.18  4512.2 1273.39  4531.8 1279.53
  4572.2 1274.35  4602.4 1266.46  4662.5 1265.74  4693.2 1271.53  4723.5 1265.96
  4763.8 1266.10  4794.1 1269.24  4814.6 1269.37  4861.8 1270.50  4915.2 1269.86
  4925.2 1267.70  4936.2 1266.99  4955.5 1266.47  4975.7 1262.85  4985.8 1259.63
  4991.0 1259.56  4991.5 1259.06  4999.9 1259.56  5016.0 1260.06  5036.1 1264.17
  5076.2 1267.59  5136.5 1269.37  5155.6 1268.66  5166.6 1270.22  5333.4 1271.40
#Mann=7,-1,0
  4335.1    0.05       0  4662.5    0.12       0  4814.6    0.05       0
  4861.8    0.12       0  4936.2    0.05       0  4991.0    0.03       0
  4999.9    0.05       0
Bank Sta=4991,4999.9
Exp/Cntr=0.3,0.1

Type RM Length L Ch R = 1,2000,500,500,500
BEGIN DESCRIPTION:
PRAIRIE MT SPRING BRANCH 4.0
END DESCRIPTION:
XS GIS Cut Line= 3
      2762605.66     10194553.11      2763118.59     10194612.82
      2763650.82     10194569.37
#Sta/Elev= 30
  4483.6 1284.16  4544.0 1281.51  4611.4 1277.19  4755.5 1270.91  4783.5 1268.73
  4788.5 1269.49  4846.1 1264.05  4856.1 1264.01  4866.2 1261.38  4877.0 1260.78
  4896.4 1260.84  4906.5 1262.52  4926.6 1263.35  4946.7 1260.43  5002.6 1258.90
  5003.1 1258.40  5011.6 1258.90  5017.2 1259.05  5027.2 1262.06  5037.2 1263.41
  5047.2 1263.68  5055.1 1264.85  5060.1 1263.94  5087.4 1267.40  5127.5 1267.84
  5176.7 1266.53  5278.0 1267.57  5338.2 1270.89  5408.4 1271.46  5534.0 1276.63
#Mann=3,-1,0
  4483.6    0.05       0  5002.6    0.05       0  5011.6    0.05       0
Bank Sta=5002.6,5011.6
Exp/Cntr=0.3,0.1

Type RM Length L Ch R = 1,1500,500,500,500
BEGIN DESCRIPTION:
PRAIRIE MT SPRING BRANCH 3.0
END DESCRIPTION:
XS GIS Cut Line= 3
      2762535.54     10195003.38      2762931.63     10195028.72
      2763590.26     10194638.79
#Sta/Elev= 30
  4603.1 1273.73  4613.0 1273.43  4753.6 1269.29  4773.6 1267.87  4793.6 1268.48
  4863.8 1265.76  4933.9 1264.65  4964.0 1261.76  4979.3 1256.54  4979.8 1256.04
  4988.8 1256.54  4989.7 1257.64  5015.7 1258.33  5037.1 1261.52  5095.6 1261.36
  5122.9 1263.45  5183.0 1265.34  5239.8 1266.73  5361.2 1265.95  5562.5 1266.03
  5606.5 1268.33  5620.6 1268.34  5627.9 1269.46  5633.7 1269.23  5666.9 1271.61
  5713.6 1272.99  5723.4 1273.99  5736.9 1273.75  5744.9 1274.60  5765.4 1274.61
#Mann=8,-1,0
  4603.1    0.12       0  4613.0    0.05       0  4979.3    0.03       0
  4988.8    0.05       0  5183.0    0.12       0  5361.2    0.05       0
  5666.9    0.12       0  5736.9    0.05       0
Bank Sta=4979.3,4988.8
Exp/Cntr=0.3,0.1

Type RM Length L Ch R = 1,1000,0,0,0
BEGIN DESCRIPTION:
PRAIRIE MT SPRING BRANCH 2.0
END DESCRIPTION:
XS GIS Cut Line= 4
      2762596.31     10195550.26      2763135.46     10195475.55
      2763477.41     10195337.58      2763633.65     10194673.55
#Sta/Elev= 30
  4455.7 1287.25  4596.4 1276.98  4798.3 1265.63  4869.0 1263.59  4906.4 1260.84
  4911.4 1262.57  4959.8 1258.35  4978.4 1253.90  4978.9 1253.40  4987.9 1253.90
  4997.6 1255.35  5042.3 1256.36  5047.7 1257.87  5064.9 1255.86  5071.8 1257.77
  5077.2 1256.01  5086.5 1259.50  5096.0 1261.14  5208.7 1263.85  5334.5 1271.21
  5423.1 1271.61  5428.3 1270.54  5527.4 1268.80  5602.9 1268.82  5772.4 1272.90
  5777.5 1274.00  5862.3 1273.19  5929.2 1275.02  5973.2 1276.12  6050.9 1276.36
#Mann=5,-1,0
  4455.7    0.05       0  4978.4    0.03       0  4987.9    0.05       0
  5929.2    0.12       0  5973.2    0.05       0
Bank Sta=4978.4,4987.9
Exp/Cntr=0.3,0.1

Chan Stop Cuts=-1