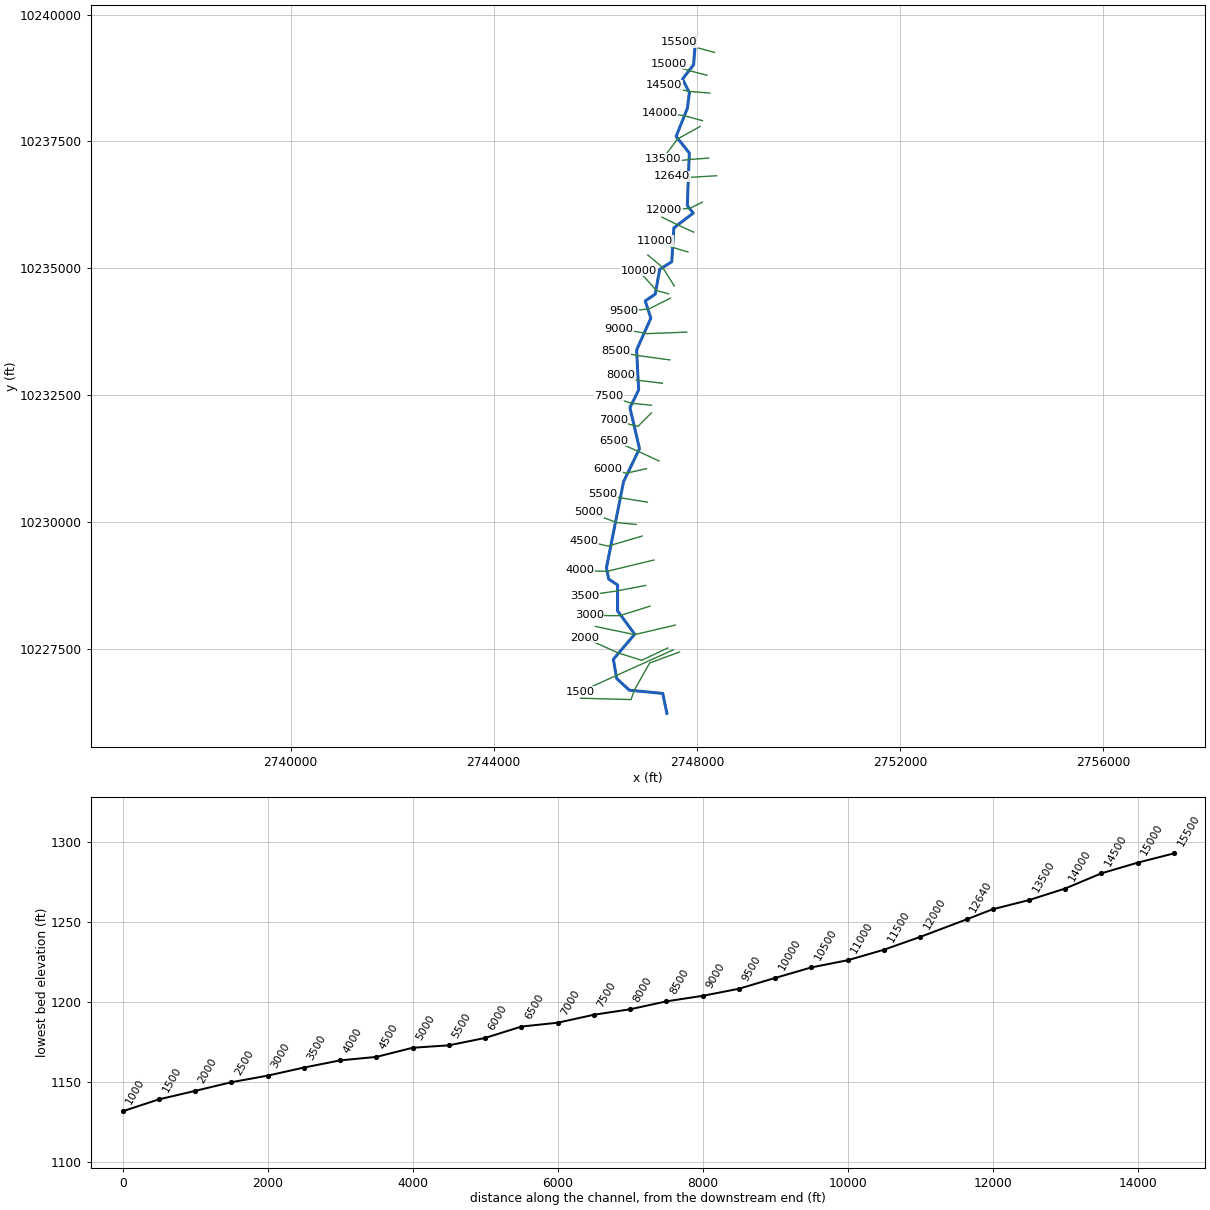
--- RHODES CREEK.prj (project) ---

Proj Title=RHODES CREEK Base Level Engineering
Current Plan=p01
Default Exp/Contr=0.3,0.1
English Units
Geom File=g01
Flow File=f01
Plan File=p01
BEGIN DESCRIPTION:
RHODES CREEK
END DESCRIPTION:

--- RHODES CREEK.p01 (plan) ---

Plan Title=Multiple Run
Short Identifier=Multiple
Geom File=g01
Flow File=f01
Subcritical Flow
K Sum by GR= 0
Std Step Tol= 0.01
Critical Tol= 0.01
Num of Std Step Trials= 20
Max Error Tol= 0.3
Flow Tol Ratio= 0.001
Split Flow NTrial= 30
Split Flow Tol= 0.02
Split Flow Ratio= 0.02
Log Output Level= 0
Friction Slope Method= 1
Unsteady Friction Slope Method= 2
Unsteady Bridges Friction Slope Method= 1
Parabolic Critical Depth
Global Vel Dist=  1 , 1 , 1
Global Log Level= 0
CheckData=True
Encroach Param= -1, 0, 0, 0
BEGIN DESCRIPTION:
Multiple Run
END DESCRIPTION:

--- RHODES CREEK.f01 (steady flow) ---

Flow Title=Multiple
Number of Profiles=7
Profile Names=10-year,25-year,50-year,1pct_min,100-year,1pct_plu,500-year
River Rch & RM= RHODES CREEK,Reach-1,15500
     435     702     976     740    1304    2297    1796
River Rch & RM= RHODES CREEK,Reach-1,9500
     806    1366    1910    1329    2615    5146    3613
Boundary for River Rch & Prof#=RHODES CREEK,Reach-1,1
Up Type=0
Dn Type=3
Dn Slope=0.005
Boundary for River Rch & Prof#=RHODES CREEK,Reach-1,2
Up Type=0
Dn Type=3
Dn Slope=0.005
Boundary for River Rch & Prof#=RHODES CREEK,Reach-1,3
Up Type=0
Dn Type=3
Dn Slope=0.005
Boundary for River Rch & Prof#=RHODES CREEK,Reach-1,4
Up Type=0
Dn Type=3
Dn Slope=0.005
Boundary for River Rch & Prof#=RHODES CREEK,Reach-1,5
Up Type=0
Dn Type=3
Dn Slope=0.005
Boundary for River Rch & Prof#=RHODES CREEK,Reach-1,6
Up Type=0
Dn Type=3
Dn Slope=0.005
Boundary for River Rch & Prof#=RHODES CREEK,Reach-1,7
Up Type=0
Dn Type=3
Dn Slope=0.005

--- RHODES CREEK.g01 (geometry) ---

Geom Title=Existing Conditions

River Reach=RHODES CREEK,Reach-1
Reach XY= 30
      2747974.25     10239532.00      2747937.25     10239014.00
      2747718.25     10238728.00      2747853.50     10238462.00
      2747814.75     10238158.00      2747592.00     10237598.00
      2747851.50     10237273.00      2747812.75     10236239.00
      2747928.50     10236089.00      2747547.00     10235795.00
      2747506.75     10235130.00      2747269.25     10234980.00
      2747180.75     10234492.00      2746984.25     10234358.00
      2747094.25     10234019.00      2746814.50     10233391.00
      2746854.50     10232604.00      2746683.25     10232254.00
      2746870.50     10231447.00      2746557.00     10230795.00
      2746220.50     10229100.00      2746264.25     10228878.00
      2746439.25     10228760.00      2746439.50     10228250.00
      2746776.75     10227791.00      2746356.75     10227297.00
      2746420.75     10226919.00      2746670.75     10226688.00
      2747329.50     10226624.00      2747410.25     10226231.00

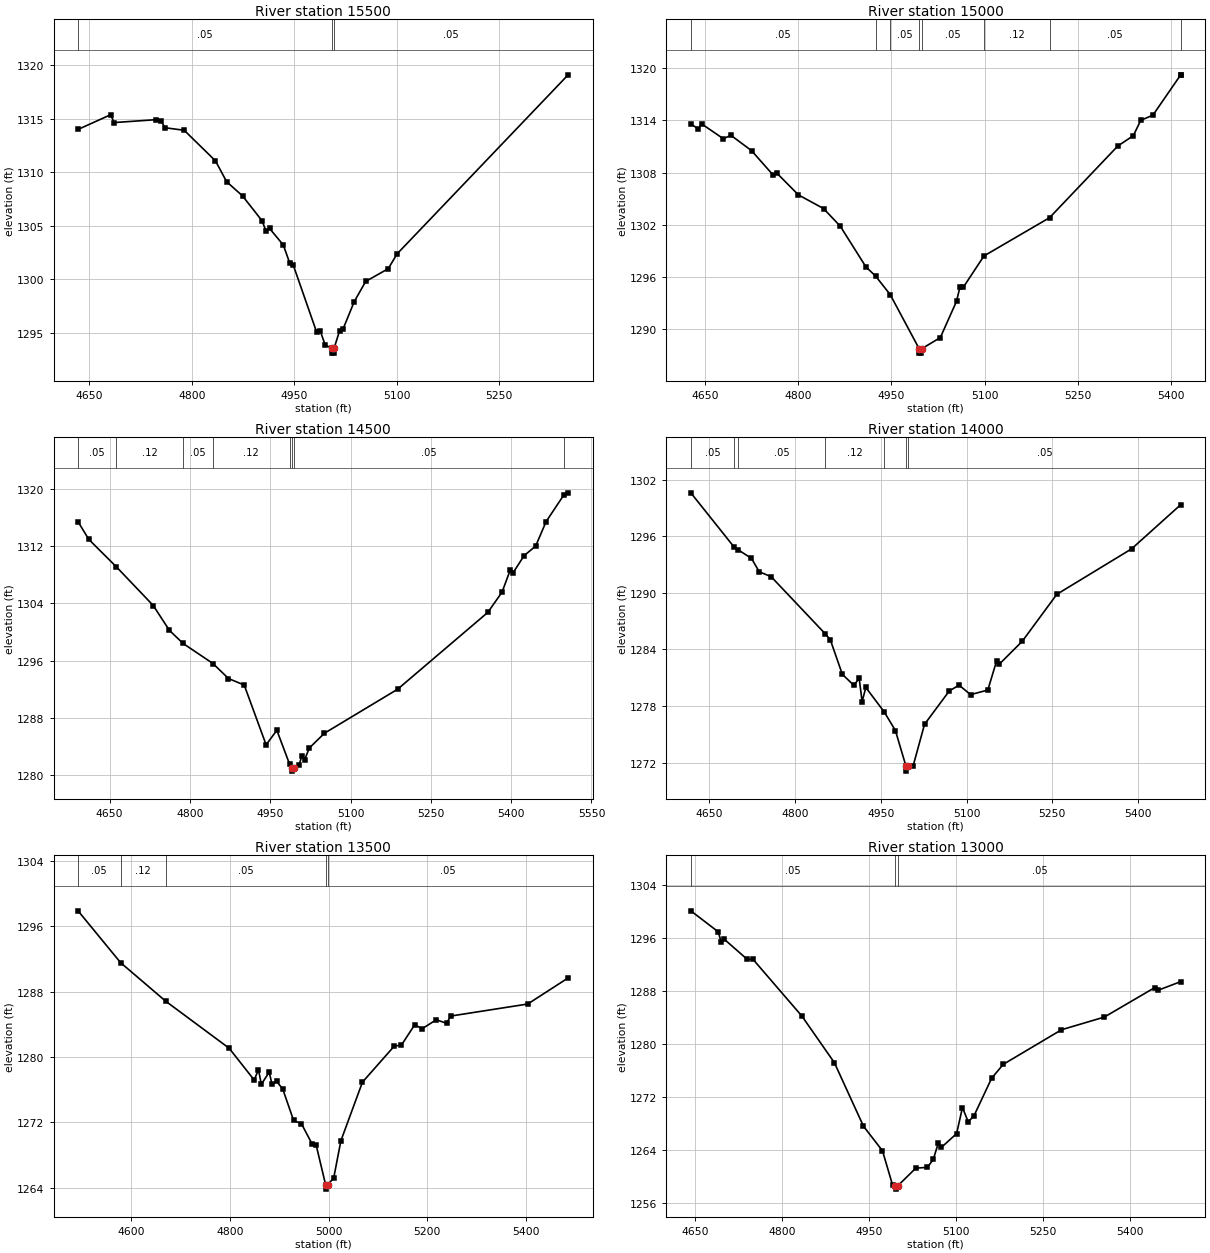
Type RM Length L Ch R = 1,15500,500,500,500
BEGIN DESCRIPTION:
RHODES CREEK 31.0
END DESCRIPTION:
XS GIS Cut Line= 3
      2748345.70     10239255.25      2747992.11     10239352.06
      2747655.66     10239453.12
#Sta/Elev= 30
  4633.4 1313.99  4681.1 1315.36  4686.3 1314.63  4747.5 1314.90  4755.2 1314.81
  4760.4 1314.15  4788.9 1313.91  4834.6 1311.06  4851.1 1309.10  4874.3 1307.78
  4903.0 1305.45  4908.7 1304.49  4913.9 1304.74  4934.1 1303.19  4943.2 1301.55
  4948.4 1301.36  4982.9 1295.05  4988.1 1295.18  4995.6 1293.81  5004.7 1293.59
  5005.0 1293.09  5008.5 1293.09  5008.7 1293.59  5016.5 1295.18  5021.7 1295.36
  5038.0 1297.91  5054.8 1299.79  5087.8 1300.98  5100.7 1302.36  5351.3 1319.09
#Mann=3,-1,0
  4633.4    0.05       0  5004.7    0.05       0  5008.7    0.05       0
Bank Sta=5004.7,5008.7
Exp/Cntr=0.3,0.1

Type RM Length L Ch R = 1,15000,500,500,500
BEGIN DESCRIPTION:
RHODES CREEK 30.0
END DESCRIPTION:
XS GIS Cut Line= 3
      2748198.08     10238803.87      2747837.83     10238899.01
      2747442.95     10239029.55
#Sta/Elev= 30
  4627.4 1313.58  4639.5 1312.99  4644.7 1313.58  4679.8 1311.87  4691.9 1312.27
  4725.2 1310.50  4760.3 1307.67  4765.5 1307.95  4800.6 1305.43  4840.9 1303.87
  4867.8 1301.85  4909.1 1297.18  4924.9 1296.11  4948.1 1294.01  4994.8 1287.79
  4995.0 1287.29  4998.5 1287.29  4998.8 1287.79  5028.8 1289.07  5054.9 1293.23
  5060.5 1294.90  5065.8 1294.84  5099.0 1298.43  5204.6 1302.82  5314.4 1311.04
  5339.3 1312.22  5351.3 1313.98  5370.9 1314.58  5415.6 1319.20  5415.9 1319.20
#Mann=8,-1,0
  4627.4    0.05       0  4924.9    0.12       0  4948.1    0.05       0
  4994.8    0.05       0  4998.8    0.05       0  5099.0    0.12       0
  5204.6    0.05       0  5415.6    0.12       0
Bank Sta=4994.8,4998.8
Exp/Cntr=0.3,0.1

Type RM Length L Ch R = 1,14500,500,500,500
BEGIN DESCRIPTION:
RHODES CREEK 29.0
END DESCRIPTION:
XS GIS Cut Line= 3
      2748255.73     10238453.11      2747848.22     10238485.60
      2747355.64     10238603.12
#Sta/Elev= 30
  4591.2 1315.41  4611.3 1312.94  4662.8 1309.11  4731.7 1303.71  4761.8 1300.25
  4787.4 1298.42  4843.2 1295.62  4872.1 1293.53  4901.5 1292.62  4942.4 1284.28
  4962.4 1286.31  4986.2 1281.59  4990.5 1281.11  4990.8 1280.61  4994.5 1281.11
  5003.9 1281.47  5009.3 1282.75  5014.4 1282.23  5023.2 1283.85  5051.4 1285.90
  5188.0 1292.04  5356.4 1302.76  5383.0 1305.59  5398.5 1308.72  5403.7 1308.30
  5424.1 1310.67  5445.8 1312.02  5465.2 1315.42  5498.7 1319.18  5506.4 1319.44
#Mann=8,-1,0
  4591.2    0.05       0  4662.8    0.12       0  4787.4    0.05       0
  4843.2    0.12       0  4986.2    0.05       0  4990.5    0.03       0
  4994.5    0.05       0  5498.7    0.12       0
Bank Sta=4990.5,4994.5
Exp/Cntr=0.3,0.1

Type RM Length L Ch R = 1,14000,500,500,500
BEGIN DESCRIPTION:
RHODES CREEK 28.0
END DESCRIPTION:
XS GIS Cut Line= 3
      2748111.31     10237909.77      2747742.02     10238010.16
      2747270.00     10238065.94
#Sta/Elev= 30
  4617.3 1300.60  4692.7 1294.88  4700.6 1294.54  4723.5 1293.65  4737.1 1292.23
  4757.9 1291.71  4852.5 1285.66  4861.5 1285.02  4882.6 1281.35  4902.9 1280.18
  4912.0 1280.95  4917.2 1278.46  4923.7 1279.96  4956.1 1277.35  4975.5 1275.39
  4994.1 1271.59  4994.3 1271.09  4998.1 1271.59  5006.4 1271.62  5026.5 1276.06
  5069.8 1279.59  5086.9 1280.21  5107.1 1279.20  5137.3 1279.69  5152.7 1282.79
  5157.7 1282.45  5197.7 1284.87  5258.1 1289.84  5389.0 1294.66  5475.3 1299.36
#Mann=7,-1,0
  4617.3    0.05       0  4692.7    0.12       0  4700.6    0.05       0
  4852.5    0.12       0  4956.1    0.05       0  4994.1    0.03       0
  4998.1    0.05       0
Bank Sta=4994.1,4998.1
Exp/Cntr=0.3,0.1

Type RM Length L Ch R = 1,13500,500,500,500
BEGIN DESCRIPTION:
RHODES CREEK 27.0
END DESCRIPTION:
XS GIS Cut Line= 3
      2748067.92     10237796.93      2747623.60     10237550.66
      2747330.40     10237163.69
#Sta/Elev= 30
  4492.0 1297.86  4578.2 1291.53  4669.8 1286.81  4798.3 1281.07  4849.0 1277.19
  4857.8 1278.44  4863.5 1276.66  4879.5 1278.14  4885.2 1276.68  4894.7 1277.01
  4907.0 1276.07  4929.0 1272.24  4944.8 1271.85  4966.5 1269.36  4974.8 1269.20
  4994.0 1264.35  4994.2 1263.85  4998.0 1264.35  5010.3 1265.23  5024.8 1269.76
  5068.5 1276.92  5133.0 1281.33  5147.5 1281.45  5174.6 1283.95  5189.2 1283.44
  5218.3 1284.55  5239.1 1284.11  5247.4 1285.00  5403.5 1286.47  5485.5 1289.66
#Mann=5,-1,0
  4492.0    0.05       0  4578.2    0.12       0  4669.8    0.05       0
  4994.0    0.05       0  4998.0    0.05       0
Bank Sta=4994,4998
Exp/Cntr=0.3,0.1

Type RM Length L Ch R = 1,13000,360,360,360
BEGIN DESCRIPTION:
RHODES CREEK 26.0
END DESCRIPTION:
XS GIS Cut Line= 3
      2748232.87     10237171.93      2747876.51     10237146.03
      2747390.81     10237093.80
#Sta/Elev= 30
  4642.7 1300.04  4690.0 1296.88  4695.2 1295.33  4700.2 1295.78  4740.1 1292.73
  4750.2 1292.72  4834.4 1284.19  4890.5 1277.17  4940.7 1267.60  4973.5 1263.90
  4990.8 1258.77  4995.9 1258.63  4996.2 1258.13  4999.9 1258.63  5031.0 1261.29
  5051.1 1261.41  5061.2 1262.62  5070.1 1265.14  5075.2 1264.42  5101.4 1266.49
  5111.5 1270.42  5121.5 1268.25  5131.6 1269.21  5161.8 1274.82  5181.9 1276.92
  5282.4 1282.13  5356.3 1284.04  5443.2 1288.47  5448.3 1288.05  5488.5 1289.39
#Mann=3,-1,0
  4642.7    0.05       0  4995.9    0.05       0  4999.9    0.05       0
Bank Sta=4995.9,4999.9
Exp/Cntr=0.3,0.1

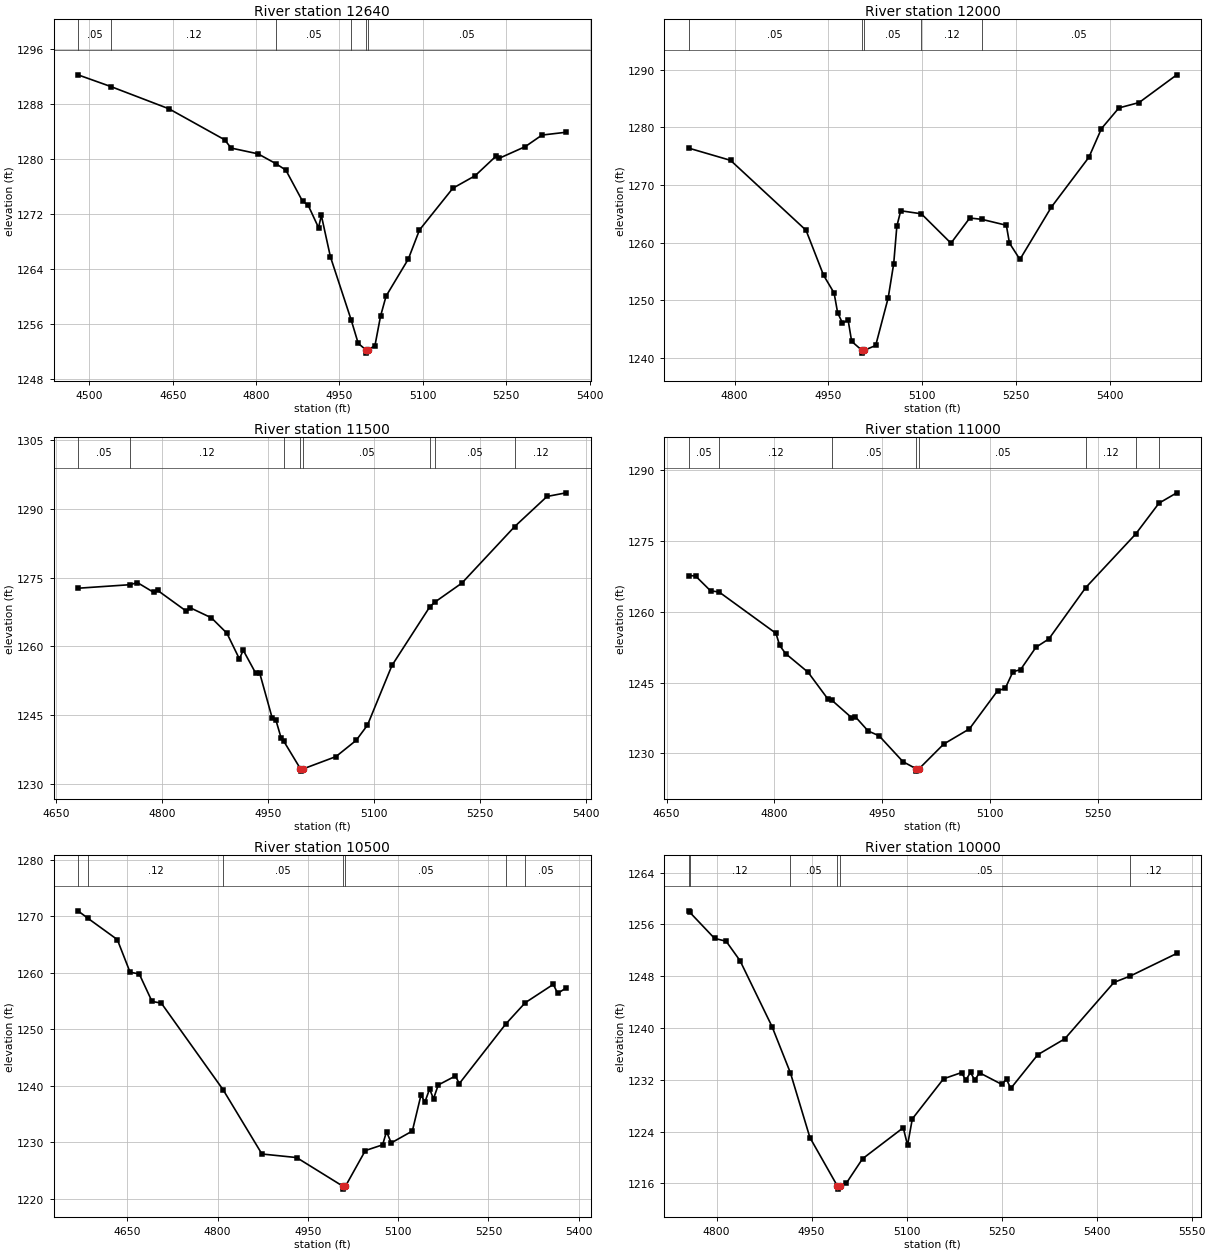
Type RM Length L Ch R = 1,12640,640,640,640
BEGIN DESCRIPTION:
RHODES CREEK 25.0
END DESCRIPTION:
XS GIS Cut Line= 3
      2748389.13     10236824.70      2747869.50     10236793.00
      2747512.34     10236816.02
#Sta/Elev= 30
  4479.4 1292.25  4539.1 1290.53  4643.2 1287.31  4743.3 1282.81  4755.1 1281.60
  4803.5 1280.76  4835.2 1279.35  4853.5 1278.40  4883.6 1273.87  4893.6 1273.30
  4912.4 1270.02  4917.4 1271.81  4933.7 1265.80  4971.0 1256.63  4983.8 1253.19
  4997.4 1252.28  4997.7 1251.78  5001.4 1252.28  5013.8 1252.84  5023.9 1257.14
  5033.9 1260.07  5074.0 1265.47  5094.0 1269.69  5154.1 1275.76  5194.2 1277.58
  5232.1 1280.45  5237.1 1280.10  5284.4 1281.81  5314.5 1283.49  5357.9 1283.90
#Mann=6,-1,0
  4479.4    0.05       0  4539.1    0.12       0  4835.2    0.05       0
  4971.0    0.12       0  4997.4    0.05       0  5001.4    0.05       0
Bank Sta=4997.4,5001.4
Exp/Cntr=0.3,0.1

Type RM Length L Ch R = 1,12000,500,500,500
BEGIN DESCRIPTION:
RHODES CREEK 24.0
END DESCRIPTION:
XS GIS Cut Line= 3
      2748105.68     10236303.11      2747861.01     10236181.35
      2747355.70     10236153.11
#Sta/Elev= 30
  4726.7 1276.40  4793.7 1274.27  4914.2 1262.13  4942.2 1254.32  4959.0 1251.24
  4964.6 1247.84  4972.4 1246.01  4981.4 1246.54  4987.0 1242.85  5003.3 1241.30
  5003.6 1240.80  5007.3 1241.30  5025.4 1242.13  5045.4 1250.41  5054.2 1256.36
  5059.2 1262.85  5065.4 1265.52  5098.3 1264.99  5145.6 1259.89  5175.6 1264.26
  5194.8 1264.03  5234.0 1263.00  5239.0 1259.90  5255.7 1257.07  5305.8 1266.14
  5365.9 1274.82  5385.9 1279.79  5413.7 1283.37  5446.0 1284.31  5506.1 1289.12
#Mann=5,-1,0
  4726.7    0.05       0  5003.3    0.05       0  5007.3    0.05       0
  5098.3    0.12       0  5194.8    0.05       0
Bank Sta=5003.3,5007.3
Exp/Cntr=0.3,0.1

Type RM Length L Ch R = 1,11500,500,500,500
BEGIN DESCRIPTION:
RHODES CREEK 23.0
END DESCRIPTION:
XS GIS Cut Line= 3
      2747937.71     10235713.58      2747647.30     10235844.84
      2747313.31     10236008.43
#Sta/Elev= 30
  4681.3 1272.66  4754.7 1273.43  4765.5 1273.88  4788.6 1271.75  4794.1 1272.18
  4834.8 1267.64  4840.3 1268.39  4870.1 1266.21  4892.0 1262.86  4909.7 1257.25
  4915.1 1259.15  4932.8 1254.13  4938.3 1254.23  4955.9 1244.47  4961.4 1243.89
  4968.9 1239.91  4972.4 1239.33  4996.1 1233.29  4996.4 1232.79  5000.1 1233.29
  5046.3 1235.96  5074.9 1239.50  5090.9 1242.82  5125.5 1255.82  5179.3 1268.67
  5186.7 1269.69  5224.5 1273.79  5299.1 1286.10  5344.9 1292.67  5371.9 1293.46
#Mann=8,-1,0
  4681.3    0.05       0  4754.7    0.12       0  4972.4    0.05       0
  4996.1    0.05       0  5000.1    0.05       0  5179.3    0.12       0
  5186.7    0.05       0  5299.1    0.12       0
Bank Sta=4996.1,5000.1
Exp/Cntr=0.3,0.1

Type RM Length L Ch R = 1,11000,500,500,500
BEGIN DESCRIPTION:
RHODES CREEK 22.0
END DESCRIPTION:
XS GIS Cut Line= 3
      2747824.89     10235322.95      2747518.76     10235413.73
      2747182.48     10235539.98
#Sta/Elev= 30
  4680.7 1267.70  4690.3 1267.62  4711.2 1264.46  4723.1 1264.21  4802.1 1255.45
  4807.3 1252.87  4815.5 1251.15  4846.8 1247.18  4873.8 1241.61  4879.6 1241.28
  4907.0 1237.58  4912.2 1237.79  4930.2 1234.73  4945.5 1233.70  4978.7 1228.21
  4997.0 1226.71  4997.2 1226.21  5001.0 1226.71  5035.3 1231.95  5071.0 1235.17
  5110.1 1243.25  5120.8 1243.77  5131.5 1247.29  5142.1 1247.74  5163.5 1252.49
  5181.4 1254.25  5232.7 1265.15  5301.9 1276.47  5334.5 1283.06  5359.2 1285.25
#Mann=8,-1,0
  4680.7    0.05       0  4723.1    0.12       0  4879.6    0.05       0
  4997.0    0.05       0  5001.0    0.05       0  5232.7    0.12       0
  5301.9    0.05       0  5334.5    0.12       0
Bank Sta=4997,5001
Exp/Cntr=0.3,0.1

Type RM Length L Ch R = 1,10500,500,500,500
BEGIN DESCRIPTION:
RHODES CREEK 21.0
END DESCRIPTION:
XS GIS Cut Line= 3
      2747555.69     10234653.10      2747326.02     10235019.23
      2747034.90     10235262.22
#Sta/Elev= 30
  4567.8 1270.93  4584.1 1269.63  4633.2 1265.85  4654.4 1260.08  4669.7 1259.77
  4690.9 1254.91  4706.3 1254.62  4809.0 1239.31  4873.6 1227.94  4931.3 1227.31
  5008.4 1222.23  5008.7 1221.73  5012.4 1222.23  5045.5 1228.55  5074.2 1229.56
  5080.7 1231.91  5088.5 1229.90  5123.6 1232.00  5138.0 1238.37  5144.5 1237.13
  5152.3 1239.44  5158.8 1237.69  5166.6 1240.14  5195.2 1241.73  5201.7 1240.39
  5278.8 1250.91  5311.2 1254.68  5357.9 1257.93  5365.2 1256.34  5379.2 1257.29
#Mann=7,-1,0
  4567.8    0.05       0  4584.1    0.12       0  4809.0    0.05       0
  5008.4    0.03       0  5012.4    0.05       0  5278.8    0.12       0
  5311.2    0.05       0
Bank Sta=5008.4,5012.4
Exp/Cntr=0.3,0.1

Type RM Length L Ch R = 1,10000,500,500,500
BEGIN DESCRIPTION:
RHODES CREEK 20.0
END DESCRIPTION:
XS GIS Cut Line= 3
      2747442.94     10234498.30      2747206.90     10234560.88
      2746855.68     10234953.12
#Sta/Elev= 30
  4755.8 1258.11  4757.9 1257.86  4796.8 1253.85  4815.0 1253.42  4837.0 1250.41
  4887.5 1240.24  4916.6 1233.07  4947.3 1223.10  4990.6 1215.63  4990.9 1215.13
  4994.6 1215.63  5004.7 1216.03  5030.4 1219.82  5094.7 1224.61  5101.5 1221.91
  5109.0 1225.98  5158.3 1232.17  5186.7 1233.13  5193.4 1231.98  5200.9 1233.15
  5207.6 1231.97  5215.1 1233.10  5250.2 1231.31  5257.7 1232.10  5264.4 1230.68
  5307.1 1235.89  5349.7 1238.34  5427.4 1247.06  5452.9 1248.03  5526.5 1251.53
#Mann=6,-1,0
  4755.8    0.05       0  4757.9    0.12       0  4916.6    0.05       0
  4990.6    0.03       0  4994.6    0.05       0  5452.9    0.12       0
Bank Sta=4990.6,4994.6
Exp/Cntr=0.3,0.1

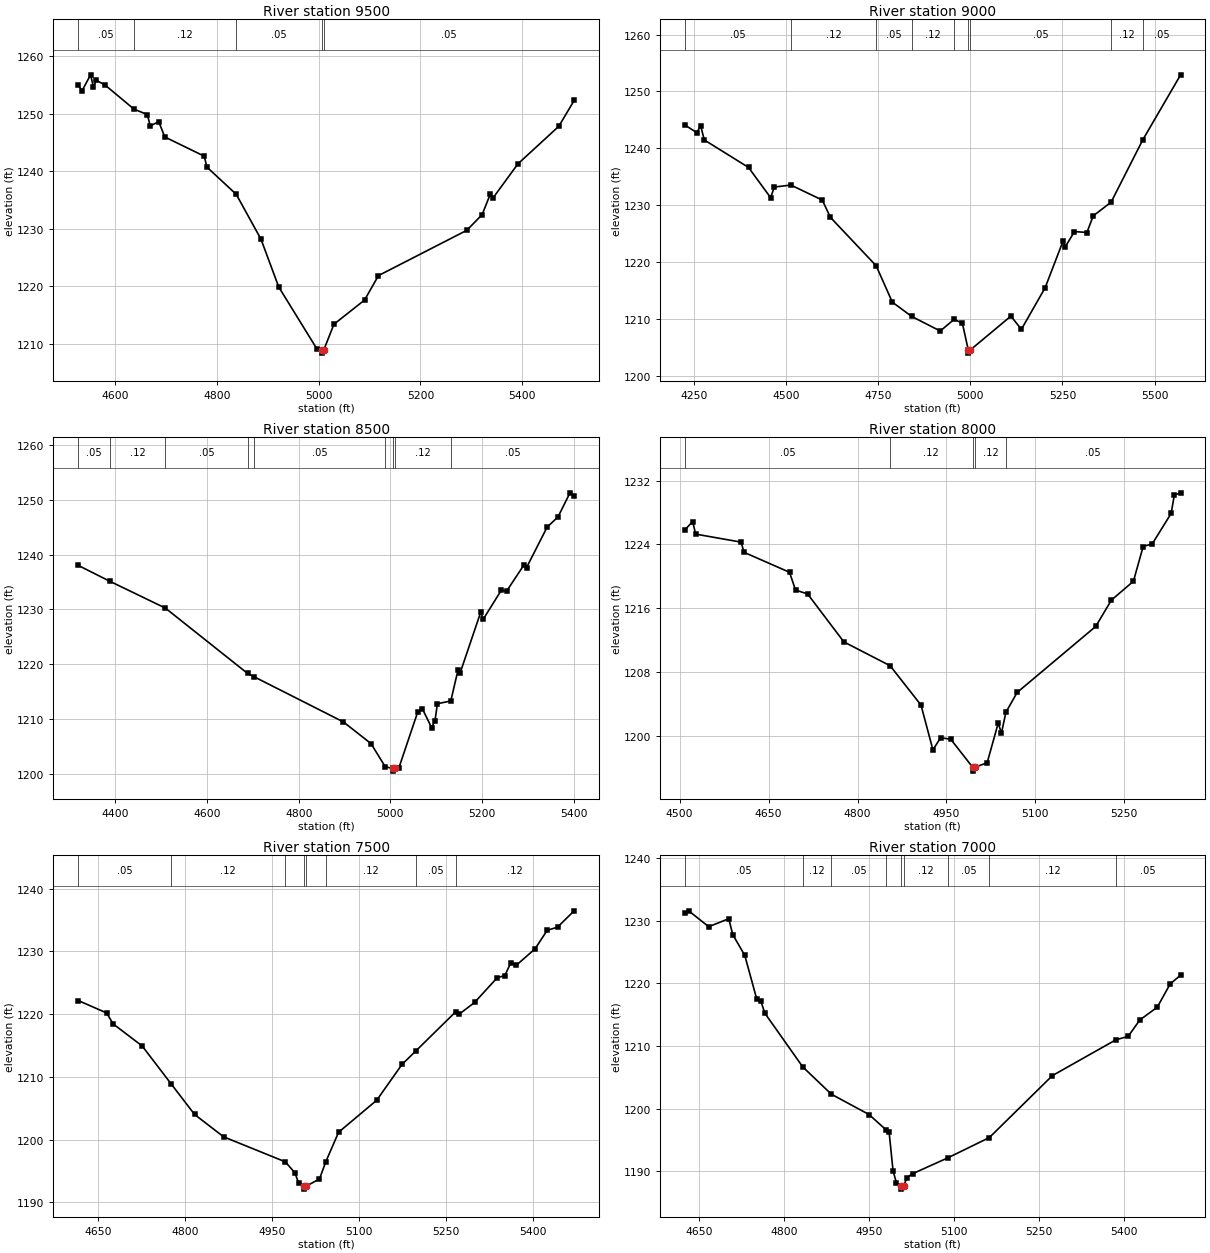
Type RM Length L Ch R = 1,9500,500,500,500
BEGIN DESCRIPTION:
RHODES CREEK 19.0
END DESCRIPTION:
XS GIS Cut Line= 3
      2747477.60     10234411.49      2747055.65     10234199.08
      2746555.66     10234153.11
#Sta/Elev= 30
  4527.6 1254.98  4535.2 1254.03  4551.9 1256.79  4557.5 1254.69  4563.3 1255.82
  4579.9 1255.05  4637.3 1250.81  4663.5 1249.88  4669.1 1247.89  4685.8 1248.65
  4697.7 1245.98  4775.1 1242.64  4780.7 1240.72  4838.1 1236.00  4886.7 1228.20
  4921.6 1219.88  4997.2 1209.02  5005.7 1208.87  5006.0 1208.37  5009.9 1208.87
  5030.1 1213.40  5090.3 1217.61  5117.6 1221.86  5291.2 1229.74  5321.3 1232.47
  5337.3 1236.03  5342.3 1235.32  5391.6 1241.30  5471.9 1247.83  5502.1 1252.33
#Mann=5,-1,0
  4527.6    0.05       0  4637.3    0.12       0  4838.1    0.05       0
  5005.7    0.05       0  5009.9    0.05       0
Bank Sta=5005.7,5009.9
Exp/Cntr=0.3,0.1

Type RM Length L Ch R = 1,9000,500,500,500
BEGIN DESCRIPTION:
RHODES CREEK 18.0
END DESCRIPTION:
XS GIS Cut Line= 3
      2747798.84     10233743.10      2747024.10     10233713.50
      2746461.96     10233812.55
#Sta/Elev= 30
  4224.7 1244.11  4257.9 1242.73  4267.9 1244.00  4277.9 1241.46  4398.0 1236.62
  4458.0 1231.30  4468.0 1233.17  4513.0 1233.52  4598.1 1230.88  4620.3 1227.83
  4744.5 1219.31  4788.3 1212.91  4841.0 1210.39  4918.4 1207.83  4955.9 1209.88
  4978.4 1209.22  4994.6 1204.44  4994.8 1203.94  4998.9 1204.44  5110.1 1210.45
  5138.6 1208.13  5203.0 1215.44  5252.1 1223.73  5257.2 1222.60  5282.7 1225.34
  5316.5 1225.17  5333.5 1228.09  5382.1 1230.51  5468.2 1241.49  5570.8 1252.92
#Mann=9,-1,0
  4224.7    0.05       0  4513.0    0.12       0  4744.5    0.05       0
  4841.0    0.12       0  4955.9    0.05       0  4994.6    0.05       0
  4998.9    0.05       0  5382.1    0.12       0  5468.2    0.05       0
Bank Sta=4994.6,4998.9
Exp/Cntr=0.3,0.1

Type RM Length L Ch R = 1,8500,500,500,500
BEGIN DESCRIPTION:
RHODES CREEK 17.0
END DESCRIPTION:
XS GIS Cut Line= 3
      2747468.93     10233196.23      2746793.79     10233287.66
      2746401.20     10233369.85
#Sta/Elev= 30
  4318.7 1238.03  4387.5 1235.14  4508.9 1230.24  4688.3 1218.32  4703.2 1217.68
  4897.2 1209.48  4957.7 1205.52  4989.0 1201.26  5006.1 1200.99  5006.4 1200.49
  5010.5 1200.99  5018.5 1201.06  5059.4 1211.21  5069.6 1211.90  5090.0 1208.43
  5097.5 1209.72  5102.6 1212.79  5131.9 1213.29  5147.4 1218.86  5152.5 1218.47
  5197.4 1229.55  5202.5 1228.18  5242.2 1233.51  5253.5 1233.31  5292.1 1238.18
  5297.2 1237.63  5342.1 1245.01  5365.9 1246.88  5392.0 1251.27  5401.1 1250.76
#Mann=9,-1,0
  4318.7    0.05       0  4387.5    0.12       0  4508.9    0.05       0
  4688.3    0.12       0  4703.2    0.05       0  4989.0    0.12       0
  5006.1    0.07       0  5010.5    0.12       0  5131.9    0.05       0
Bank Sta=5006.1,5010.5
Exp/Cntr=0.3,0.1

Type RM Length L Ch R = 1,8000,500,500,500
BEGIN DESCRIPTION:
RHODES CREEK 16.0
END DESCRIPTION:
XS GIS Cut Line= 3
      2747321.35     10232736.16      2746833.45     10232795.54
      2746505.65     10232903.12
#Sta/Elev= 30
  4508.5 1225.78  4521.9 1226.86  4527.0 1225.28  4603.6 1224.27  4608.7 1222.99
  4685.3 1220.49  4695.5 1218.25  4715.7 1217.78  4777.0 1211.75  4855.0 1208.76
  4907.1 1203.82  4927.2 1198.20  4940.4 1199.74  4957.5 1199.51  4994.1 1196.03
  4994.4 1195.53  4998.6 1196.03  5018.7 1196.58  5037.4 1201.57  5042.7 1200.27
  5050.3 1202.91  5069.2 1205.40  5201.8 1213.69  5228.3 1217.00  5265.4 1219.36
  5281.8 1223.72  5297.2 1224.06  5329.0 1227.87  5334.4 1230.18  5345.0 1230.46
#Mann=5,-1,0
  4508.5    0.05       0  4855.0    0.12       0  4994.1    0.07       0
  4998.6    0.12       0  5050.3    0.05       0
Bank Sta=4994.1,4998.6
Exp/Cntr=0.3,0.1

Type RM Length L Ch R = 1,7500,500,500,500
BEGIN DESCRIPTION:
RHODES CREEK 15.0
END DESCRIPTION:
XS GIS Cut Line= 3
      2747105.67     10232303.11      2746722.57     10232339.29
      2746271.04     10232475.74
#Sta/Elev= 30
  4615.2 1222.17  4664.4 1220.18  4675.5 1218.44  4725.7 1214.92  4776.0 1208.84
  4816.1 1204.01  4866.3 1200.44  4972.9 1196.45  4989.6 1194.68  4995.9 1193.04
  5004.9 1192.60  5005.2 1192.10  5009.4 1192.60  5031.9 1193.72  5042.7 1196.45
  5064.9 1201.17  5130.8 1206.28  5174.3 1211.97  5198.4 1214.14  5267.3 1220.39
  5273.0 1219.98  5299.7 1221.86  5338.9 1225.81  5351.9 1226.14  5362.4 1228.20
  5371.9 1227.80  5404.2 1230.41  5425.1 1233.36  5443.0 1233.87  5471.7 1236.47
#Mann=8,-1,0
  4615.2    0.05       0  4776.0    0.12       0  4972.9    0.05       0
  5004.9    0.05       0  5009.4    0.05       0  5042.7    0.12       0
  5198.4    0.05       0  5267.3    0.12       0
Bank Sta=5004.9,5009.4
Exp/Cntr=0.3,0.1

Type RM Length L Ch R = 1,7000,500,500,500
BEGIN DESCRIPTION:
RHODES CREEK 14.0
END DESCRIPTION:
XS GIS Cut Line= 3
      2747105.69     10232153.12      2746842.06     10231886.43
      2746355.66     10232003.12
#Sta/Elev= 30
  4625.0 1231.31  4632.1 1231.61  4667.4 1229.07  4702.8 1230.35  4709.8 1227.82
  4731.1 1224.47  4752.3 1217.45  4759.4 1217.18  4766.4 1215.25  4833.3 1206.66
  4883.8 1202.29  4950.3 1199.04  4981.0 1196.54  4985.7 1196.29  4992.7 1190.06
  4998.8 1188.07  5007.2 1187.61  5007.5 1187.11  5011.8 1187.61  5016.8 1188.95
  5027.1 1189.57  5089.8 1192.13  5162.6 1195.35  5273.9 1205.26  5386.0 1210.99
  5407.6 1211.53  5428.2 1214.16  5459.0 1216.20  5481.7 1219.91  5500.2 1221.33
#Mann=9,-1,0
  4625.0    0.05       0  4833.3    0.12       0  4883.8    0.05       0
  4981.0    0.12       0  5007.2    0.07       0  5011.8    0.12       0
  5089.8    0.05       0  5162.6    0.12       0  5386.0    0.05       0
Bank Sta=5007.2,5011.8
Exp/Cntr=0.3,0.1

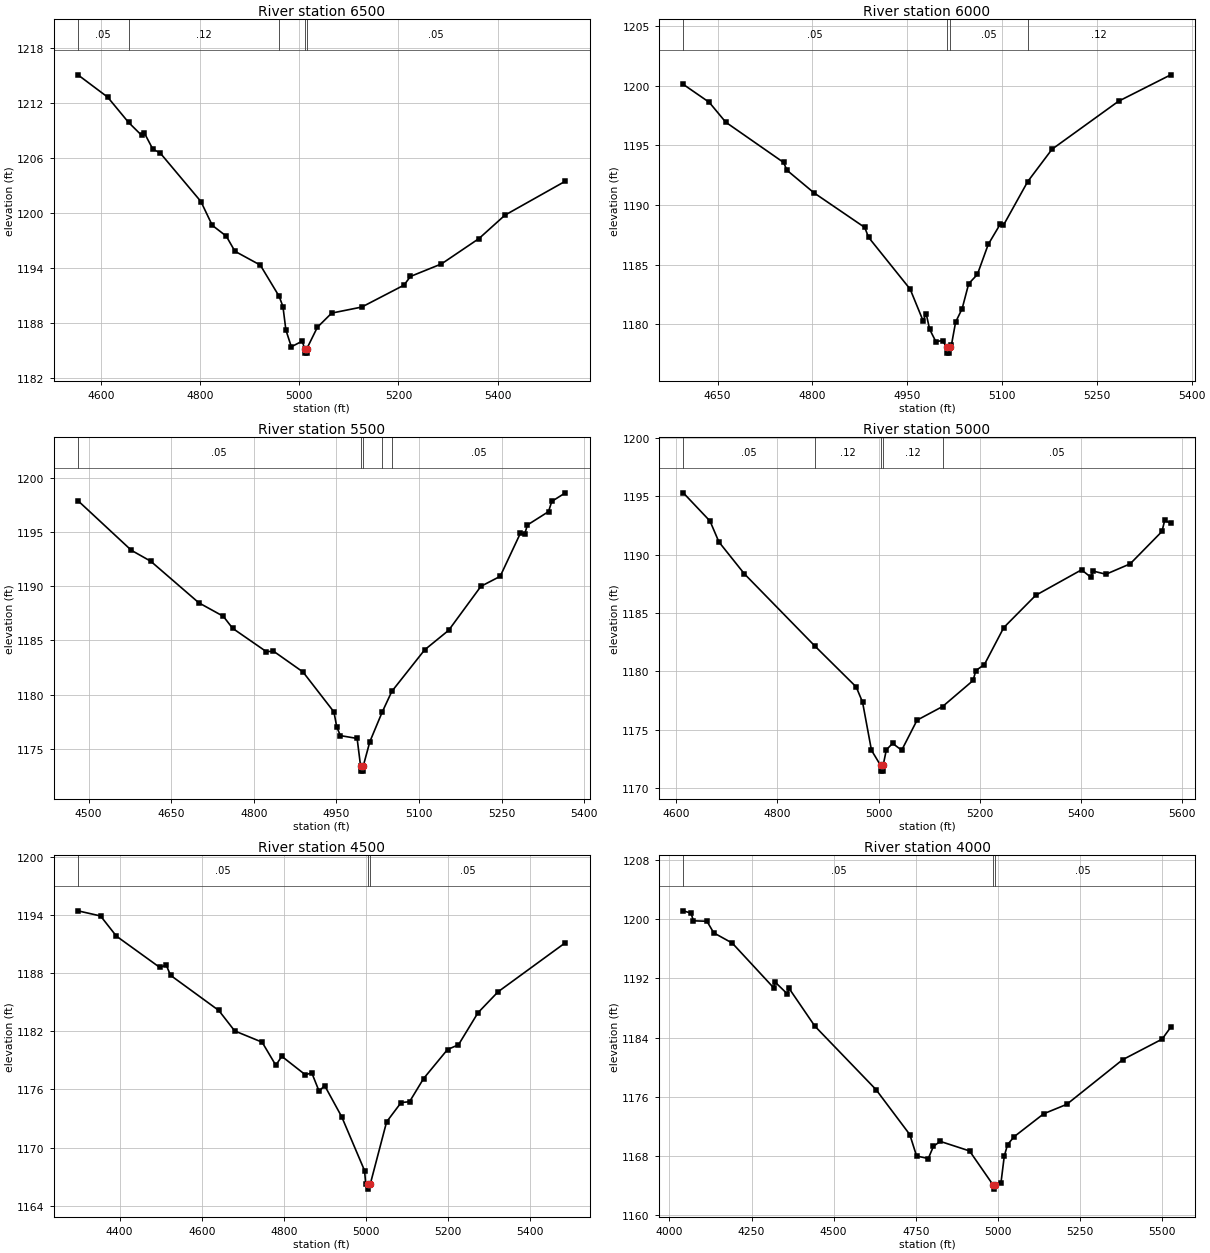
Type RM Length L Ch R = 1,6500,500,500,500
BEGIN DESCRIPTION:
RHODES CREEK 13.0
END DESCRIPTION:
XS GIS Cut Line= 3
      2747255.68     10231203.11      2746851.11     10231392.27
      2746359.27     10231607.06
#Sta/Elev= 30
  4553.4 1215.09  4613.3 1212.66  4655.5 1209.90  4681.8 1208.49  4687.3 1208.75
  4704.6 1206.97  4719.0 1206.58  4801.5 1201.26  4824.4 1198.66  4852.7 1197.48
  4870.1 1195.83  4921.3 1194.32  4959.3 1190.91  4967.0 1189.79  4972.9 1187.24
  4983.9 1185.40  5005.9 1186.02  5010.6 1185.21  5011.0 1184.71  5015.0 1184.71
  5015.3 1185.21  5036.4 1187.53  5065.3 1189.08  5126.0 1189.74  5211.1 1192.13
  5224.2 1193.08  5286.8 1194.45  5362.5 1197.22  5414.8 1199.77  5536.7 1203.48
#Mann=5,-1,0
  4553.4    0.05       0  4655.5    0.12       0  4959.3    0.05       0
  5010.6    0.05       0  5015.3    0.05       0
Bank Sta=5010.6,5015.3
Exp/Cntr=0.3,0.1

Type RM Length L Ch R = 1,6000,500,500,500
BEGIN DESCRIPTION:
RHODES CREEK 12.0
END DESCRIPTION:
XS GIS Cut Line= 3
      2747005.70     10231053.11      2746611.52     10230963.66
      2746255.69     10231053.11
#Sta/Elev= 30
  4595.8 1200.10  4636.8 1198.60  4663.0 1196.93  4754.4 1193.56  4759.9 1192.90
  4802.6 1191.01  4882.9 1188.11  4888.8 1187.29  4954.7 1182.94  4975.0 1180.31
  4980.1 1180.87  4985.5 1179.58  4995.3 1178.55  5006.0 1178.63  5012.2 1178.08
  5012.6 1177.58  5016.8 1177.58  5017.2 1178.08  5019.9 1178.23  5026.6 1180.18
  5036.9 1181.30  5047.3 1183.40  5061.0 1184.17  5078.2 1186.69  5097.0 1188.37
  5102.1 1188.28  5140.7 1191.96  5179.2 1194.67  5284.4 1198.69  5366.9 1200.90
#Mann=4,-1,0
  4595.8    0.05       0  5012.2    0.05       0  5017.2    0.05       0
  5140.7    0.12       0
Bank Sta=5012.2,5017.2
Exp/Cntr=0.3,0.1

Type RM Length L Ch R = 1,5500,500,500,500
BEGIN DESCRIPTION:
RHODES CREEK 11.0
END DESCRIPTION:
XS GIS Cut Line= 3
      2747026.27     10230392.40      2746513.59     10230476.33
      2746155.73     10230553.10
#Sta/Elev= 30
  4480.5 1197.87  4577.5 1193.30  4612.8 1192.29  4700.2 1188.46  4744.6 1187.22
  4761.6 1186.11  4822.9 1183.96  4835.7 1184.01  4889.4 1182.09  4945.6 1178.41
  4950.7 1177.03  4957.3 1176.23  4987.7 1175.97  4993.9 1173.46  4994.3 1172.96
  4998.6 1172.96  4999.0 1173.46  5010.8 1175.67  5033.1 1178.38  5050.8 1180.31
  5110.4 1184.13  5154.0 1185.93  5212.6 1189.98  5247.6 1190.90  5284.2 1194.86
  5291.9 1194.76  5297.1 1195.63  5335.4 1196.86  5341.3 1197.80  5366.0 1198.59
#Mann=5,-1,0
  4480.5    0.05       0  4993.9    0.05       0  4999.0    0.05       0
  5033.1    0.12       0  5050.8    0.05       0
Bank Sta=4993.9,4999
Exp/Cntr=0.3,0.1

Type RM Length L Ch R = 1,5000,500,500,500
BEGIN DESCRIPTION:
RHODES CREEK 10.0
END DESCRIPTION:
XS GIS Cut Line= 3
      2746805.73     10229953.11      2746421.74     10229991.50
      2745880.53     10230192.71
#Sta/Elev= 30
  4614.1 1195.30  4666.9 1192.88  4684.5 1191.09  4734.7 1188.36  4874.5 1182.15
  4955.8 1178.66  4968.4 1177.35  4986.0 1173.23  5003.9 1171.94  5004.3 1171.44
  5008.7 1171.44  5009.1 1171.94  5015.4 1173.27  5027.8 1173.82  5045.7 1173.23
  5076.1 1175.81  5126.6 1176.98  5186.8 1179.21  5192.2 1180.06  5209.2 1180.58
  5247.5 1183.75  5310.5 1186.51  5401.2 1188.70  5419.0 1188.08  5424.3 1188.59
  5449.3 1188.32  5497.2 1189.21  5560.1 1191.99  5565.4 1192.93  5577.4 1192.70
#Mann=5,-1,0
  4614.1    0.05       0  4874.5    0.12       0  5003.9    0.07       0
  5009.1    0.12       0  5126.6    0.05       0
Bank Sta=5003.9,5009.1
Exp/Cntr=0.3,0.1

Type RM Length L Ch R = 1,4500,500,500,500
BEGIN DESCRIPTION:
RHODES CREEK 9.0
END DESCRIPTION:
XS GIS Cut Line= 3
      2746922.10     10229724.02      2746248.75     10229526.59
      2745776.22     10229637.20
#Sta/Elev= 30
  4298.3 1194.42  4353.4 1193.89  4392.0 1191.81  4497.4 1188.59  4513.4 1188.82
  4523.8 1187.77  4641.4 1184.14  4680.1 1182.03  4746.8 1180.87  4780.2 1178.49
  4794.8 1179.41  4852.3 1177.50  4867.7 1177.71  4885.7 1175.80  4899.0 1176.40
  4940.7 1173.17  4996.3 1167.62  4999.0 1166.29  5004.8 1166.21  5005.3 1165.71
  5010.1 1166.21  5050.0 1172.65  5085.3 1174.64  5105.9 1174.73  5140.1 1177.12
  5198.3 1180.11  5225.0 1180.60  5272.6 1183.91  5321.5 1186.07  5485.3 1191.13
#Mann=3,-1,0
  4298.3    0.05       0  5004.8    0.03       0  5010.1    0.05       0
Bank Sta=5004.8,5010.1
Exp/Cntr=0.3,0.1

Type RM Length L Ch R = 1,4000,500,500,500
BEGIN DESCRIPTION:
RHODES CREEK 8.0
END DESCRIPTION:
XS GIS Cut Line= 3
      2747155.69     10229253.11      2746224.78     10229028.18
      2745699.41     10229046.88
#Sta/Elev= 30
  4042.3 1201.12  4065.8 1200.81  4073.2 1199.77  4114.3 1199.71  4134.9 1198.15
  4191.4 1196.76  4317.0 1190.74  4322.1 1191.48  4358.9 1189.90  4364.0 1190.66
  4442.6 1185.55  4628.7 1176.98  4731.6 1170.90  4752.2 1168.01  4787.8 1167.66
  4803.6 1169.31  4824.2 1169.98  4913.4 1168.69  4986.1 1164.03  4986.5 1163.53
  4991.4 1164.03  5009.1 1164.38  5019.1 1167.98  5029.1 1169.54  5049.1 1170.61
  5139.2 1173.71  5209.2 1174.98  5379.3 1181.01  5499.4 1183.79  5525.7 1185.40
#Mann=3,-1,0
  4042.3    0.05       0  4986.1    0.05       0  4991.4    0.05       0
Bank Sta=4986.1,4991.4
Exp/Cntr=0.3,0.1

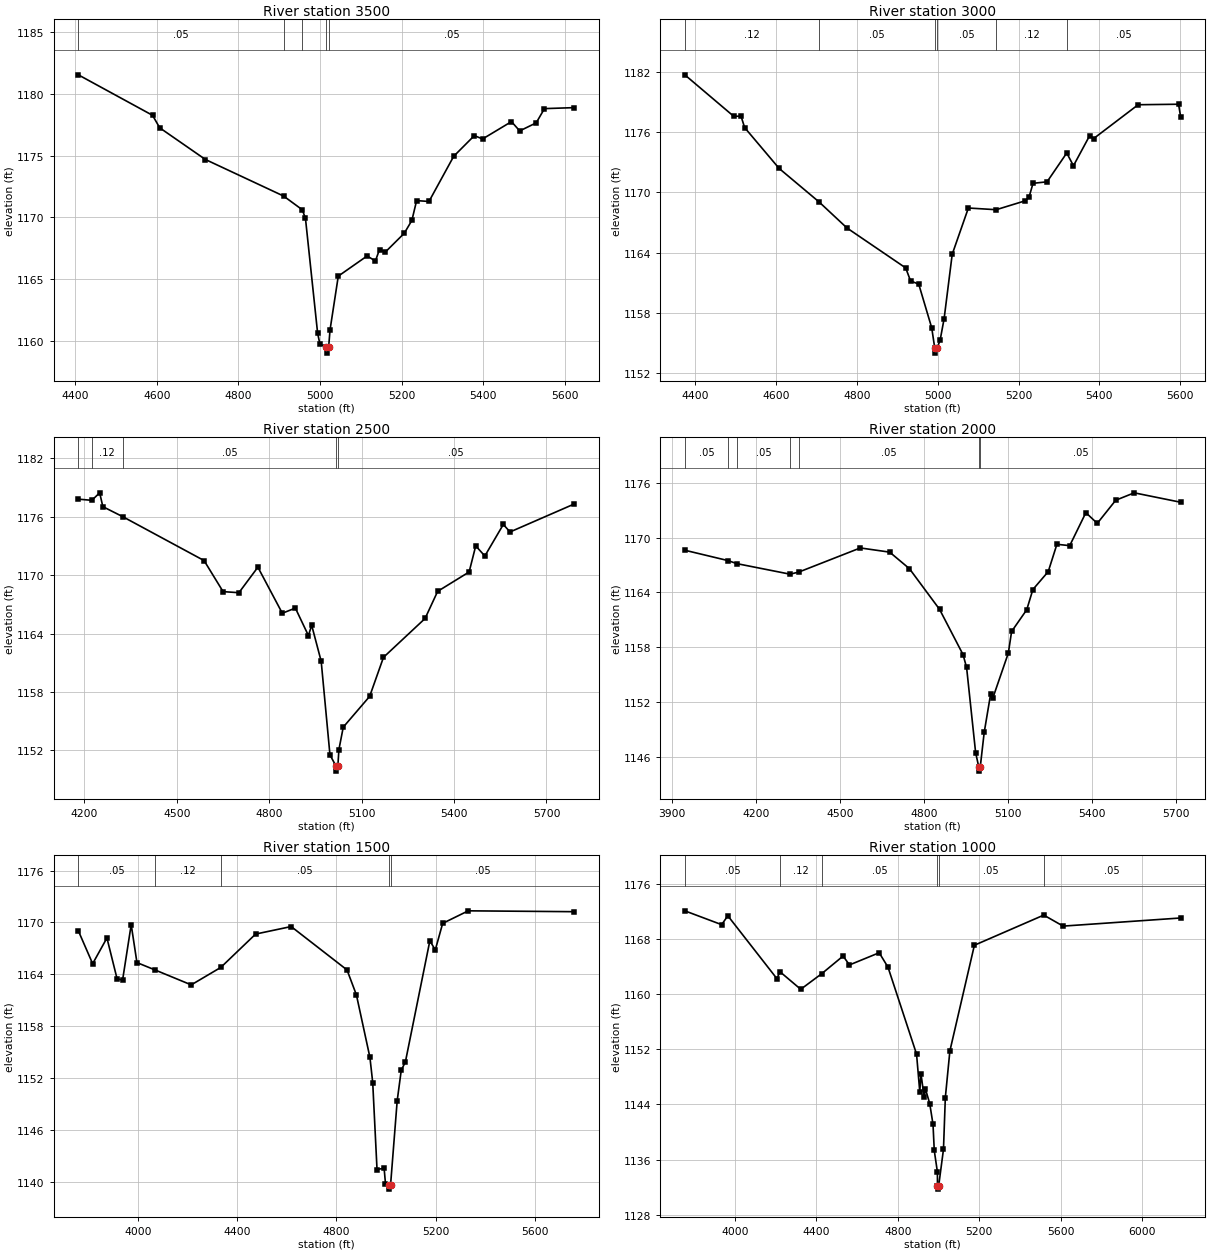
Type RM Length L Ch R = 1,3500,500,500,500
BEGIN DESCRIPTION:
RHODES CREEK 7.0
END DESCRIPTION:
XS GIS Cut Line= 3
      2746991.56     10228751.79      2746409.70     10228640.55
      2745793.61     10228552.13
#Sta/Elev= 30
  4407.6 1181.52  4589.4 1178.25  4607.0 1177.24  4719.0 1174.68  4910.4 1171.73
  4956.3 1170.62  4964.1 1169.92  4993.9 1160.64  4999.5 1159.77  5015.4 1159.54
  5015.9 1159.04  5020.9 1159.54  5024.3 1160.92  5044.5 1165.26  5115.2 1166.89
  5135.4 1166.48  5145.5 1167.41  5159.3 1167.19  5206.1 1168.72  5224.8 1169.76
  5236.4 1171.36  5266.7 1171.29  5327.3 1174.94  5377.8 1176.61  5398.1 1176.34
  5468.8 1177.74  5489.0 1176.99  5529.4 1177.64  5549.6 1178.79  5622.4 1178.87
#Mann=5,-1,0
  4407.6    0.05       0  4910.4    0.12       0  4956.3    0.05       0
  5015.4    0.05       0  5020.9    0.05       0
Bank Sta=5015.4,5020.9
Exp/Cntr=0.3,0.1

Type RM Length L Ch R = 1,3000,500,500,500
BEGIN DESCRIPTION:
RHODES CREEK 6.0
END DESCRIPTION:
XS GIS Cut Line= 3
      2747078.36     10228343.81      2746481.51     10228155.34
      2745880.54     10228161.50
#Sta/Elev= 30
  4374.1 1181.71  4495.1 1177.58  4513.2 1177.59  4522.2 1176.45  4607.6 1172.38
  4706.2 1169.05  4775.4 1166.45  4920.7 1162.47  4932.7 1161.18  4953.0 1160.85
  4985.1 1156.50  4992.6 1154.48  4993.0 1153.98  4998.2 1154.48  5005.8 1155.25
  5015.8 1157.42  5035.8 1163.83  5075.8 1168.44  5144.6 1168.27  5215.8 1169.15
  5225.8 1169.51  5235.8 1170.90  5270.5 1171.05  5319.2 1173.92  5335.8 1172.65
  5375.8 1175.64  5385.8 1175.36  5495.9 1178.73  5595.9 1178.78  5601.0 1177.54
#Mann=6,-1,0
  4374.1    0.12       0  4706.2    0.05       0  4992.6    0.05       0
  4998.2    0.05       0  5144.6    0.12       0  5319.2    0.05       0
Bank Sta=4992.6,4998.2
Exp/Cntr=0.3,0.1

Type RM Length L Ch R = 1,2500,500,500,500
BEGIN DESCRIPTION:
RHODES CREEK 5.0
END DESCRIPTION:
XS GIS Cut Line= 3
      2747573.14     10227970.54      2746775.09     10227782.48
      2746001.89     10227944.50
#Sta/Elev= 30
  4180.1 1177.82  4223.9 1177.70  4249.4 1178.47  4259.7 1177.05  4324.3 1176.02
  4588.4 1171.51  4650.1 1168.32  4701.5 1168.21  4763.1 1170.83  4842.4 1166.10
  4884.8 1166.63  4927.1 1163.81  4937.8 1164.86  4968.6 1161.17  4997.1 1151.55
  5017.0 1150.38  5017.4 1149.88  5022.7 1150.38  5026.2 1152.10  5040.3 1154.40
  5126.0 1157.56  5170.9 1161.57  5305.9 1165.56  5346.8 1168.35  5449.0 1170.34
  5470.4 1173.02  5500.0 1171.98  5560.0 1175.22  5581.8 1174.45  5790.0 1177.32
#Mann=5,-1,0
  4180.1    0.05       0  4223.9    0.12       0  4324.3    0.05       0
  5017.0    0.05       0  5022.7    0.05       0
Bank Sta=5017,5022.7
Exp/Cntr=0.3,0.1

Type RM Length L Ch R = 1,2000,500,500,500
BEGIN DESCRIPTION:
RHODES CREEK 4.0
END DESCRIPTION:
XS GIS Cut Line= 4
      2747425.52     10227519.13      2746913.39     10227276.09
      2746448.72     10227423.28      2745794.32     10227718.47
#Sta/Elev= 30
  3945.7 1168.61  4099.5 1167.48  4132.2 1167.14  4321.7 1165.99  4353.1 1166.22
  4573.1 1168.86  4678.0 1168.40  4748.6 1166.59  4856.3 1162.14  4940.2 1157.19
  4952.9 1155.78  4985.2 1146.46  4996.1 1144.94  4996.6 1144.44  5001.9 1144.94
  5015.8 1148.67  5038.9 1152.89  5047.2 1152.48  5102.1 1157.36  5113.8 1159.72
  5167.9 1162.10  5189.8 1164.31  5244.7 1166.27  5275.7 1169.26  5321.5 1169.11
  5379.2 1172.72  5420.0 1171.55  5486.0 1174.08  5552.1 1174.89  5717.9 1173.86
#Mann=7,-1,0
  3945.7    0.05       0  4099.5    0.12       0  4132.2    0.05       0
  4321.7    0.12       0  4353.1    0.05       0  4996.1    0.03       0
  5001.9    0.05       0
Bank Sta=4996.1,5001.9
Exp/Cntr=0.3,0.1

Type RM Length L Ch R = 1,1500,500,500,500
BEGIN DESCRIPTION:
RHODES CREEK 3.0
END DESCRIPTION:
XS GIS Cut Line= 3
      2747538.38     10227484.42      2746406.65     10226973.53
      2745715.44     10226659.75
#Sta/Elev= 30
  3758.3 1169.04  3816.1 1165.23  3873.7 1168.21  3914.4 1163.51  3936.8 1163.32
  3971.6 1169.75  3994.8 1165.36  4067.6 1164.51  4213.9 1162.78  4333.2 1164.80
  4473.7 1168.66  4617.1 1169.53  4842.5 1164.51  4880.4 1161.62  4935.0 1154.38
  4946.2 1151.48  4963.6 1141.41  4992.2 1141.56  4997.8 1139.76  5012.3 1139.64
  5012.8 1139.14  5018.3 1139.64  5045.0 1149.38  5061.5 1152.92  5077.9 1153.84
  5176.8 1167.89  5198.7 1166.82  5228.5 1169.90  5331.8 1171.35  5759.1 1171.25
#Mann=5,-1,0
  3758.3    0.05       0  4067.6    0.12       0  4333.2    0.05       0
  5012.3    0.03       0  5018.3    0.05       0
Bank Sta=5012.3,5018.3
Exp/Cntr=0.3,0.1

Type RM Length L Ch R = 1,1000,0,0,0
BEGIN DESCRIPTION:
RHODES CREEK 2.0
END DESCRIPTION:
XS GIS Cut Line= 5
      2747659.94     10227441.03      2747070.95     10227223.45
      2746767.42     10226685.23      2746705.68     10226503.11
      2745708.73     10226529.51
#Sta/Elev= 30
  3754.2 1172.13  3935.2 1170.12  3965.6 1171.41  4206.5 1162.28  4221.7 1163.28
  4323.7 1160.73  4427.3 1163.01  4531.7 1165.56  4563.1 1164.27  4709.0 1166.04
  4752.3 1163.94  4892.5 1151.32  4908.4 1145.83  4914.1 1148.49  4930.0 1145.02
  4935.8 1146.29  4957.4 1144.11  4973.4 1141.10  4979.5 1137.32  4995.0 1134.18
  4995.3 1132.20  4995.8 1131.70  5001.3 1132.20  5024.8 1137.49  5033.9 1145.00
  5056.2 1151.77  5176.6 1167.13  5517.4 1171.51  5612.4 1169.91  6189.6 1171.09
#Mann=6,-1,0
  3754.2    0.05       0  4221.7    0.12       0  4427.3    0.05       0
  4995.3    0.05       0  5001.3    0.05       0  5517.4    0.05       0
Bank Sta=4995.3,5001.3
Exp/Cntr=0.3,0.1

Chan Stop Cuts=-1