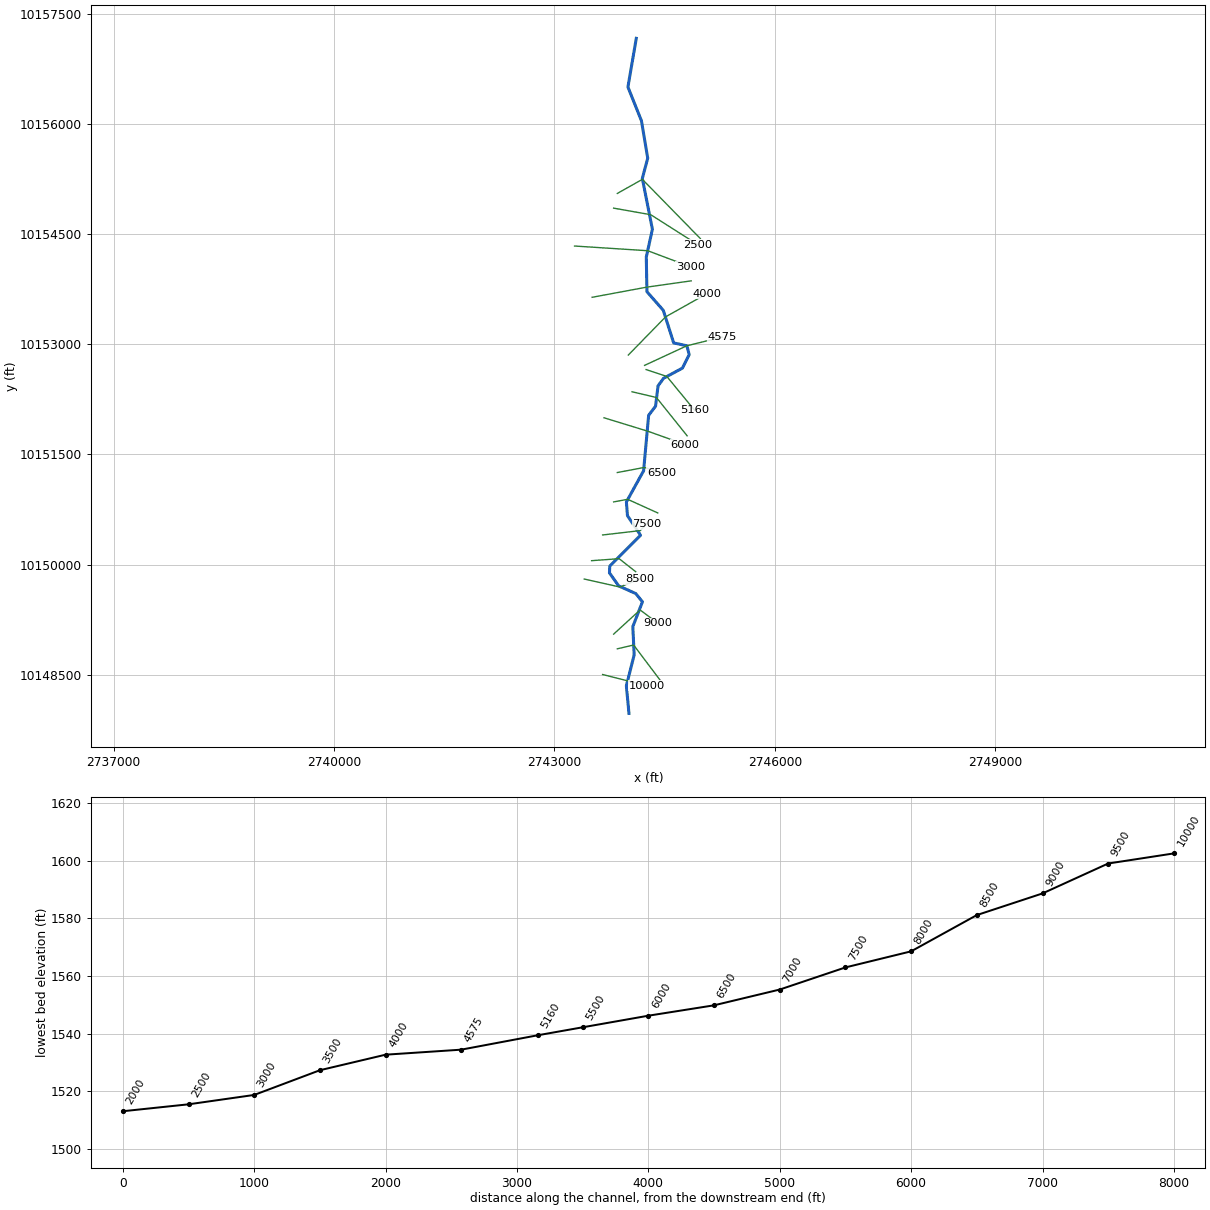
--- BERNST CREEK.prj (project) ---

Proj Title=BERNST CREEK Base Level Engineering
Current Plan=p01
Default Exp/Contr=0.3,0.1
English Units
Geom File=g01
Flow File=f01
Plan File=p01
BEGIN DESCRIPTION:
BERNST CREEK
END DESCRIPTION:

--- BERNST CREEK.p01 (plan) ---

Plan Title=Multiple Run
Short Identifier=Multiple
Geom File=g01
Flow File=f01
Subcritical Flow
K Sum by GR= 0
Std Step Tol= 0.01
Critical Tol= 0.01
Num of Std Step Trials= 20
Max Error Tol= 0.3
Flow Tol Ratio= 0.001
Split Flow NTrial= 30
Split Flow Tol= 0.02
Split Flow Ratio= 0.02
Log Output Level= 0
Friction Slope Method= 1
Unsteady Friction Slope Method= 2
Unsteady Bridges Friction Slope Method= 1
Parabolic Critical Depth
Global Vel Dist=  1 , 1 , 1
Global Log Level= 0
CheckData=True
Encroach Param= -1, 0, 0, 0
BEGIN DESCRIPTION:
Multiple Run
END DESCRIPTION:

--- BERNST CREEK.f01 (steady flow) ---

Flow Title=Multiple
Number of Profiles=7
Profile Names=10-year,25-year,50-year,1pct_min,100-year,1pct_plu,500-year
River Rch & RM= BERNST CREEK,Reach-1,10000
     209     453     751     409    1236    3732    3559
River Rch & RM= BERNST CREEK,Reach-1,8500
     235     516     860     471    1422    4293    4127
River Rch & RM= BERNST CREEK,Reach-1,2000
     241     531     887     486    1467    4430    4266
Boundary for River Rch & Prof#=BERNST CREEK,Reach-1,1
Up Type=0
Dn Type=3
Dn Slope=0.005
Boundary for River Rch & Prof#=BERNST CREEK,Reach-1,2
Up Type=0
Dn Type=3
Dn Slope=0.005
Boundary for River Rch & Prof#=BERNST CREEK,Reach-1,3
Up Type=0
Dn Type=3
Dn Slope=0.005
Boundary for River Rch & Prof#=BERNST CREEK,Reach-1,4
Up Type=0
Dn Type=3
Dn Slope=0.005
Boundary for River Rch & Prof#=BERNST CREEK,Reach-1,5
Up Type=0
Dn Type=3
Dn Slope=0.005
Boundary for River Rch & Prof#=BERNST CREEK,Reach-1,6
Up Type=0
Dn Type=3
Dn Slope=0.005
Boundary for River Rch & Prof#=BERNST CREEK,Reach-1,7
Up Type=0
Dn Type=3
Dn Slope=0.005

--- BERNST CREEK.g01 (geometry) ---

Geom Title=Existing Conditions

River Reach=BERNST CREEK,Reach-1
Reach XY= 30
      2744014.00     10147974.00      2743978.75     10148349.00
      2744085.00     10148771.00      2744066.50     10149155.00
      2744197.50     10149493.00      2744107.00     10149605.00
      2743873.75     10149710.00      2743748.75     10149887.00
      2743752.75     10149979.00      2744171.50     10150400.00
      2743993.75     10150666.00      2743979.25     10150853.00
      2744213.25     10151277.00      2744282.00     10152033.00
      2744375.75     10152156.00      2744410.00     10152433.00
      2744485.00     10152537.00      2744740.50     10152674.00
      2744834.00     10152859.00      2744801.75     10152979.00
      2744622.50     10153018.00      2744481.00     10153462.00
      2744259.00     10153715.00      2744249.75     10154187.00
      2744333.00     10154566.00      2744196.00     10155257.00
      2744269.25     10155534.00      2744184.00     10156042.00
      2744000.00     10156502.00      2744113.75     10157165.00

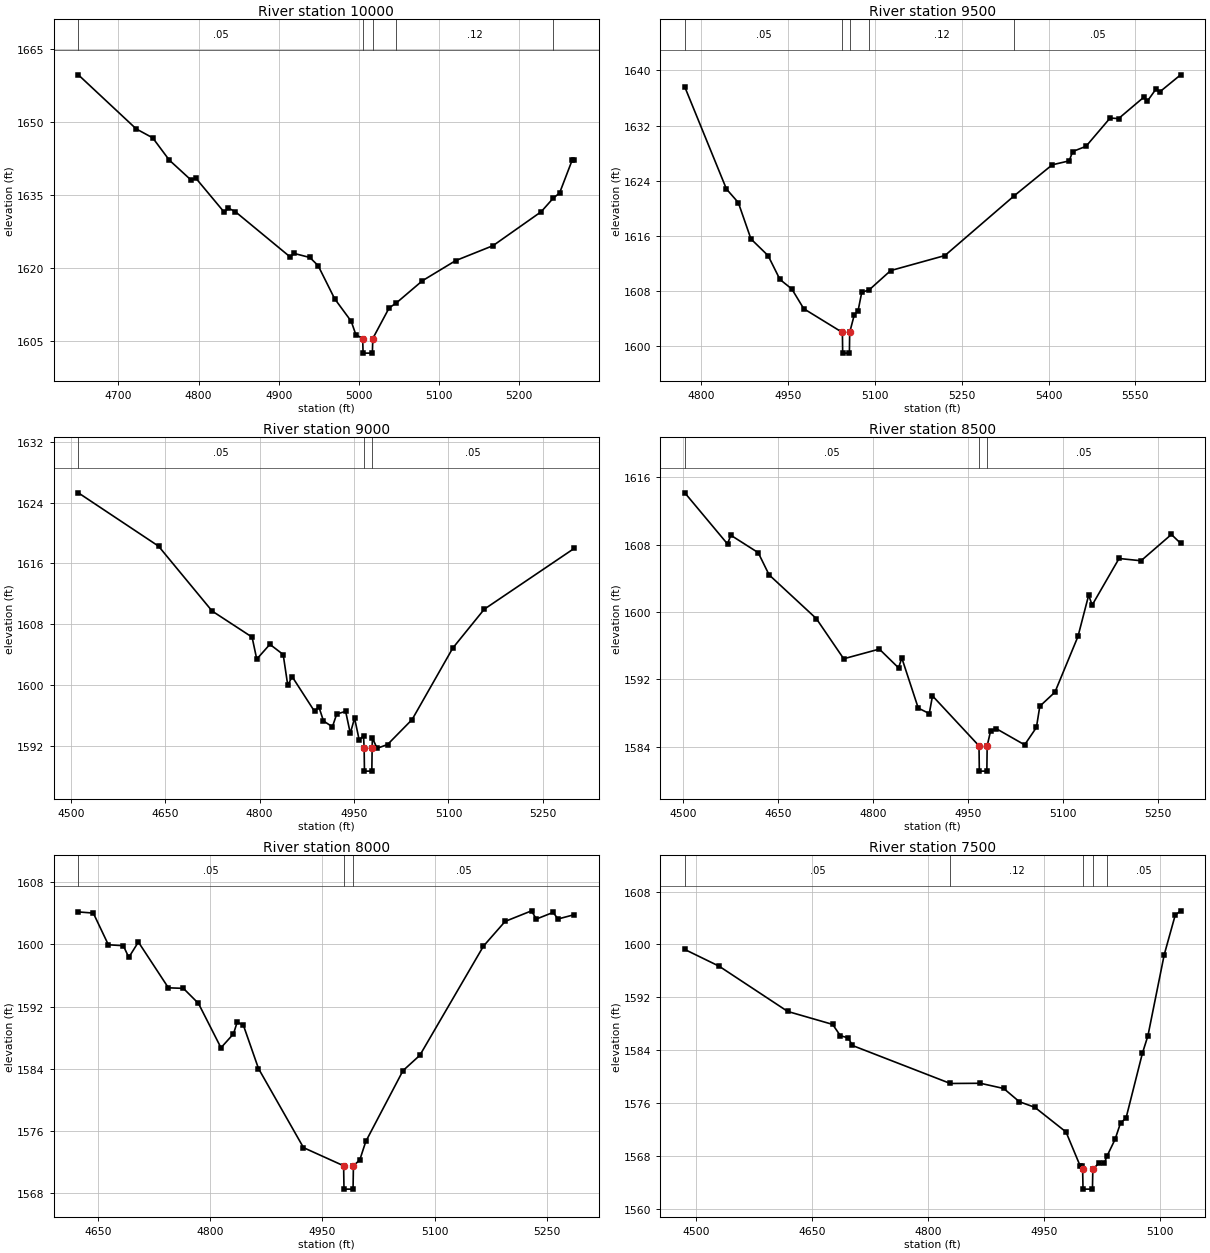
Type RM Length L Ch R = 1,10000,500,500,500
BEGIN DESCRIPTION:
BERNST CREEK 20.0
END DESCRIPTION:
XS GIS Cut Line= 3
      2743655.70     10148503.11      2743995.03     10148417.35
      2744255.73     10148353.10
#Sta/Elev= 30
  4650.0 1659.69  4722.2 1648.58  4742.8 1646.74  4763.4 1642.18  4791.0 1638.01
  4796.2 1638.53  4832.1 1631.44  4837.2 1632.30  4846.0 1631.55  4914.1 1622.29
  4919.3 1622.99  4938.8 1622.16  4949.1 1620.49  4969.7 1613.69  4990.4 1609.05
  4996.2 1606.29  5004.7 1605.51  5005.2 1602.51  5016.8 1602.51  5017.3 1605.51
  5037.7 1611.80  5046.6 1612.81  5079.2 1617.38  5120.6 1621.51  5167.3 1624.59
  5227.3 1631.55  5242.6 1634.38  5250.3 1635.40  5265.9 1642.11  5268.5 1642.11
#Mann=5,-1,0
  4650.0    0.05       0  5004.7    0.05       0  5017.3    0.05       0
  5046.6    0.12       0  5242.6    0.05       0
Bank Sta=5004.7,5017.3
Exp/Cntr=0.3,0.1

Type RM Length L Ch R = 1,9500,500,500,500
BEGIN DESCRIPTION:
BERNST CREEK 19.0
END DESCRIPTION:
XS GIS Cut Line= 3
      2743855.66     10148853.11      2744077.72     10148904.82
      2744455.66     10148403.15
#Sta/Elev= 30
  4772.0 1637.61  4843.9 1622.81  4864.4 1620.84  4886.2 1615.57  4915.8 1613.15
  4936.3 1609.69  4956.8 1608.31  4977.4 1605.45  5044.1 1602.01  5044.6 1599.01
  5056.2 1599.01  5056.7 1602.01  5064.7 1604.58  5071.2 1605.16  5077.5 1607.82
  5090.6 1608.20  5127.4 1610.98  5221.1 1613.16  5341.2 1621.86  5406.4 1626.32
  5435.6 1626.89  5441.8 1628.25  5464.7 1629.00  5506.4 1633.11  5520.9 1633.02
  5564.6 1636.13  5570.9 1635.58  5585.5 1637.30  5591.7 1636.87  5628.1 1639.37
#Mann=5,-1,0
  4772.0    0.05       0  5044.1    0.03       0  5056.7    0.05       0
  5090.6    0.12       0  5341.2    0.05       0
Bank Sta=5044.1,5056.7
Exp/Cntr=0.3,0.1

Type RM Length L Ch R = 1,9000,500,500,500
BEGIN DESCRIPTION:
BERNST CREEK 18.0
END DESCRIPTION:
XS GIS Cut Line= 3
      2743805.67     10149053.10      2744165.58     10149382.50
      2744405.67     10149203.12
#Sta/Elev= 30
  4512.1 1625.31  4639.5 1618.28  4724.6 1609.73  4788.1 1606.29  4795.5 1603.39
  4816.4 1605.34  4837.5 1604.00  4844.8 1599.92  4851.6 1601.10  4887.4 1596.49
  4894.1 1597.13  4901.5 1595.24  4915.7 1594.47  4922.5 1596.15  4936.7 1596.51
  4944.1 1593.61  4950.9 1595.62  4958.3 1592.71  4965.1 1593.32  4966.1 1591.63
  4966.6 1588.63  4978.3 1588.63  4978.8 1591.63  4979.2 1593.01  4986.6 1591.64
  5003.2 1592.13  5042.3 1595.43  5106.9 1604.85  5156.9 1609.97  5299.7 1617.98
#Mann=3,-1,0
  4512.1    0.05       0  4966.1    0.05       0  4978.8    0.05       0
Bank Sta=4966.1,4978.8
Exp/Cntr=0.3,0.1

Type RM Length L Ch R = 1,8500,500,500,500
BEGIN DESCRIPTION:
BERNST CREEK 17.0
END DESCRIPTION:
XS GIS Cut Line= 3
      2743405.73     10149803.10      2743890.96     10149694.24
      2744155.65     10149803.10
#Sta/Elev= 30
  4502.7 1614.14  4570.2 1608.07  4575.4 1609.11  4618.7 1607.04  4635.9 1604.41
  4710.5 1599.22  4753.8 1594.45  4810.1 1595.60  4840.5 1593.37  4845.6 1594.55
  4871.6 1588.60  4889.0 1587.95  4894.1 1590.05  4967.6 1584.12  4968.1 1581.12
  4980.0 1581.12  4980.5 1584.12  4985.9 1585.88  4994.6 1586.17  5039.7 1584.24
  5058.3 1586.30  5063.7 1588.82  5087.6 1590.49  5124.0 1597.10  5140.9 1602.00
  5146.4 1600.82  5188.9 1606.35  5223.6 1606.08  5271.6 1609.20  5286.2 1608.15
#Mann=3,-1,0
  4502.7    0.05       0  4967.6    0.05       0  4980.5    0.05       0
Bank Sta=4967.6,4980.5
Exp/Cntr=0.3,0.1

Type RM Length L Ch R = 1,8000,500,500,500
BEGIN DESCRIPTION:
BERNST CREEK 16.0
END DESCRIPTION:
XS GIS Cut Line= 3
      2743505.72     10150053.11      2743880.65     10150080.09
      2744105.69     10149903.10
#Sta/Elev= 30
  4624.1 1604.16  4644.1 1604.01  4664.2 1599.94  4684.2 1599.82  4691.5 1598.32
  4704.3 1600.29  4744.4 1594.41  4764.4 1594.34  4784.5 1592.41  4814.6 1586.71
  4831.3 1588.49  4836.3 1590.02  4844.6 1589.59  4864.7 1584.04  4924.8 1573.88
  4978.4 1571.55  4978.9 1568.55  4991.0 1568.55  4991.5 1571.55  5000.0 1572.30
  5008.0 1574.67  5057.7 1583.77  5080.2 1585.74  5165.2 1599.77  5194.1 1602.94
  5229.4 1604.30  5235.7 1603.24  5258.3 1604.10  5264.6 1603.25  5286.3 1603.80
#Mann=3,-1,0
  4624.1    0.05       0  4978.4    0.05       0  4991.5    0.05       0
Bank Sta=4978.4,4991.5
Exp/Cntr=0.3,0.1

Type RM Length L Ch R = 1,7500,500,500,500
BEGIN DESCRIPTION:
BERNST CREEK 15.0
END DESCRIPTION:
XS GIS Cut Line= 3
      2743655.70     10150403.11      2744166.89     10150462.27
      2744255.66     10150553.09
#Sta/Elev= 30
  4485.4 1599.24  4529.8 1596.71  4618.6 1589.86  4676.7 1587.90  4686.7 1586.19
  4696.8 1585.86  4702.3 1584.71  4829.0 1578.96  4867.9 1578.99  4898.1 1578.20
  4918.3 1576.20  4938.4 1575.35  4978.7 1571.62  4996.9 1566.51  5000.0 1566.51
  5000.2 1565.97  5000.7 1562.97  5012.9 1562.97  5013.4 1565.97  5020.9 1566.87
  5028.1 1566.86  5031.5 1567.91  5042.2 1570.51  5049.2 1572.97  5056.4 1573.74
  5077.5 1583.52  5084.7 1586.19  5105.8 1598.46  5120.0 1604.44  5127.0 1605.09
#Mann=5,-1,0
  4485.4    0.05       0  4829.0    0.12       0  5000.2    0.07       0
  5013.4    0.12       0  5031.5    0.05       0
Bank Sta=5000.2,5013.4
Exp/Cntr=0.3,0.1

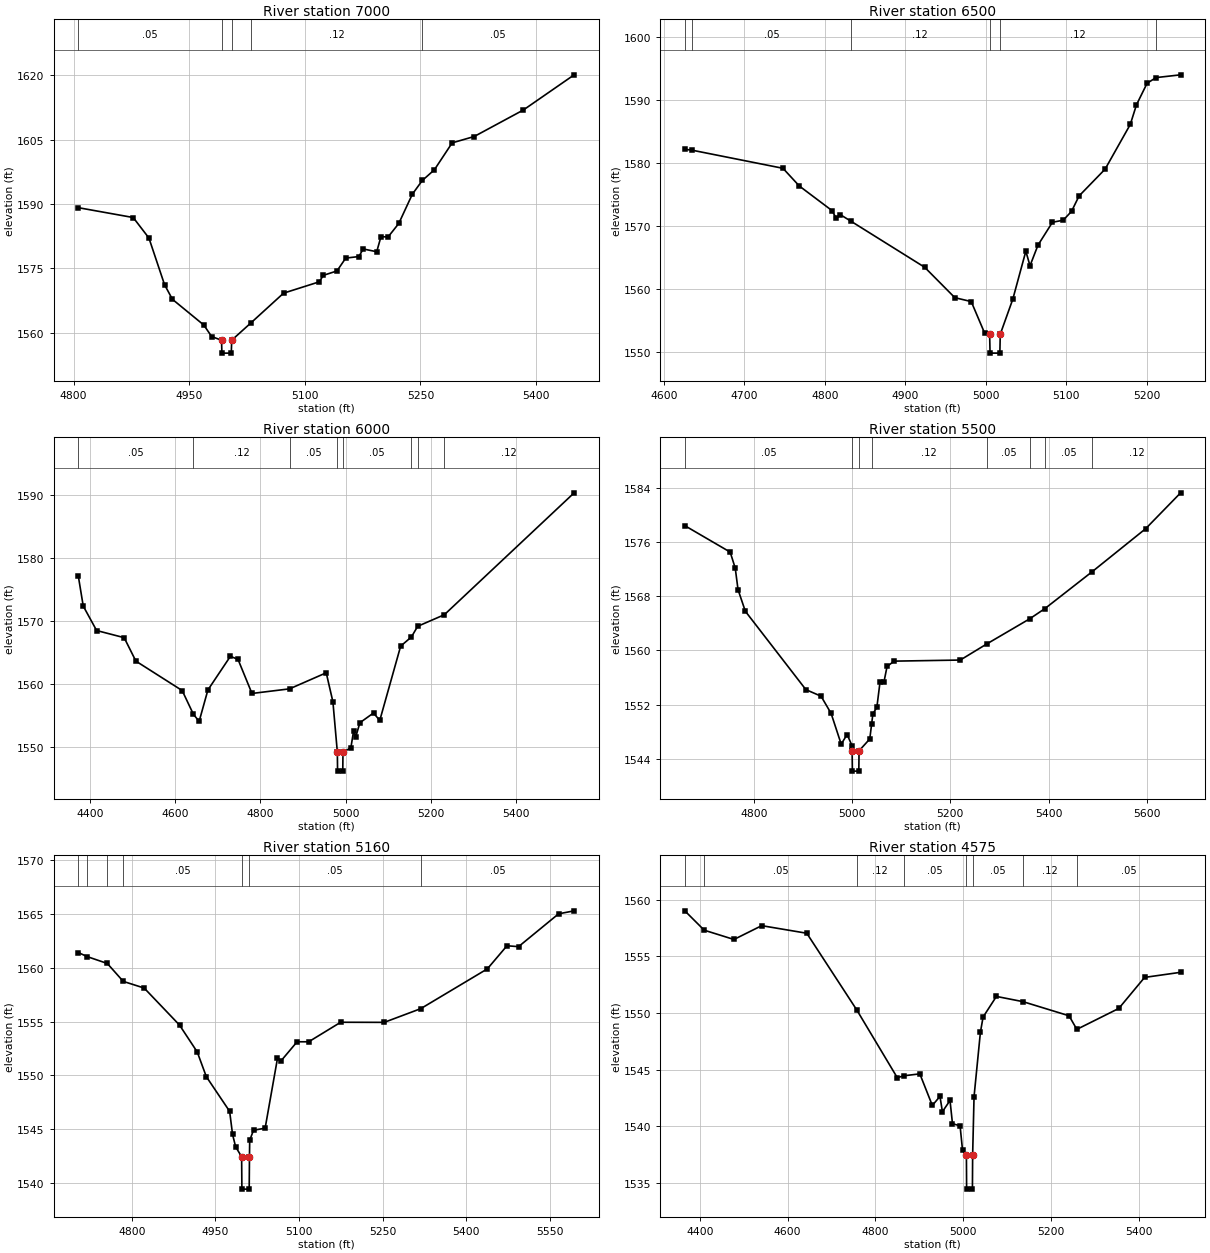
Type RM Length L Ch R = 1,7000,500,500,500
BEGIN DESCRIPTION:
BERNST CREEK 14.0
END DESCRIPTION:
XS GIS Cut Line= 3
      2743805.65     10150853.10      2743996.25     10150888.68
      2744405.67     10150703.12
#Sta/Elev= 30
  4806.1 1589.14  4877.3 1586.85  4897.7 1582.08  4918.0 1571.21  4928.2 1567.82
  4968.9 1561.84  4979.1 1559.16  4991.9 1558.30  4992.4 1555.30  5004.6 1555.30
  5005.1 1558.30  5030.4 1562.39  5072.4 1569.25  5118.6 1571.88  5124.1 1573.40
  5141.7 1574.42  5153.1 1577.41  5170.2 1577.77  5175.7 1579.54  5193.3 1578.89
  5198.8 1582.40  5208.0 1582.32  5221.9 1585.46  5239.5 1592.27  5252.5 1595.48
  5268.1 1597.95  5291.2 1604.22  5319.8 1605.70  5383.6 1611.87  5449.5 1620.05
#Mann=5,-1,0
  4806.1    0.05       0  4991.9    0.05       0  5005.1    0.05       0
  5030.4    0.12       0  5252.5    0.05       0
Bank Sta=4991.9,5005.1
Exp/Cntr=0.3,0.1

Type RM Length L Ch R = 1,6500,500,500,500
BEGIN DESCRIPTION:
BERNST CREEK 13.0
END DESCRIPTION:
XS GIS Cut Line= 3
      2743855.72     10151253.12      2744223.42     10151322.55
      2744455.66     10151253.12
#Sta/Elev= 30
  4625.8 1582.21  4634.4 1582.08  4747.9 1579.19  4768.2 1576.38  4808.9 1572.47
  4814.2 1571.22  4819.3 1571.82  4832.5 1570.78  4924.1 1563.47  4961.6 1558.64
  4982.0 1558.02  4998.6 1553.03  5004.9 1552.83  5005.4 1549.83  5017.6 1549.83
  5018.1 1552.83  5033.7 1558.40  5049.9 1566.02  5055.1 1563.71  5065.0 1566.98
  5083.0 1570.62  5096.3 1570.94  5106.7 1572.34  5116.1 1574.80  5148.5 1579.06
  5179.8 1586.16  5187.5 1589.28  5200.7 1592.70  5211.8 1593.60  5242.4 1594.04
#Mann=6,-1,0
  4625.8    0.12       0  4634.4    0.05       0  4832.5    0.12       0
  5004.9    0.07       0  5018.1    0.12       0  5211.8    0.05       0
Bank Sta=5004.9,5018.1
Exp/Cntr=0.3,0.1

Type RM Length L Ch R = 1,6000,500,500,500
BEGIN DESCRIPTION:
BERNST CREEK 12.0
END DESCRIPTION:
XS GIS Cut Line= 3
      2743674.72     10151998.64      2744274.04     10151814.76
      2744778.88     10151634.06
#Sta/Elev= 30
  4373.1 1577.08  4384.6 1572.35  4416.0 1568.48  4480.6 1567.35  4508.1 1563.64
  4616.7 1558.98  4643.0 1555.23  4656.5 1554.10  4677.0 1559.07  4729.8 1564.40
  4747.7 1563.91  4780.4 1558.52  4868.6 1559.25  4954.6 1561.79  4970.3 1557.19
  4980.7 1549.23  4981.2 1546.23  4993.4 1546.23  4993.9 1549.23  5012.4 1549.92
  5018.7 1552.54  5024.0 1551.69  5033.6 1553.89  5065.5 1555.43  5080.2 1554.25
  5129.2 1566.01  5154.4 1567.46  5169.2 1569.15  5231.7 1570.98  5536.2 1590.27
#Mann=8,-1,0
  4373.1    0.05       0  4643.0    0.12       0  4868.6    0.05       0
  4980.7    0.05       0  4993.9    0.05       0  5154.4    0.12       0
  5169.2    0.05       0  5231.7    0.12       0
Bank Sta=4980.7,4993.9
Exp/Cntr=0.3,0.1

Type RM Length L Ch R = 1,5500,340,340,340
BEGIN DESCRIPTION:
BERNST CREEK 11.0
END DESCRIPTION:
XS GIS Cut Line= 3
      2744055.72     10152353.10      2744387.25     10152275.03
      2744805.66     10151753.15
#Sta/Elev= 30
  4659.4 1578.41  4751.8 1574.51  4762.1 1572.14  4767.8 1568.97  4782.6 1565.79
  4905.9 1554.23  4936.8 1553.26  4957.3 1550.72  4977.8 1546.19  4989.9 1547.61
  5000.0 1545.94  5000.1 1545.21  5000.6 1542.21  5013.7 1542.21  5014.2 1545.21
  5036.0 1546.95  5039.8 1549.16  5042.4 1550.68  5050.4 1551.60  5056.8 1555.31
  5064.8 1555.33  5071.2 1557.64  5085.6 1558.43  5220.3 1558.59  5274.8 1560.99
  5361.6 1564.67  5392.8 1566.19  5489.0 1571.63  5597.7 1577.96  5668.9 1583.25
#Mann=8,-1,0
  4659.4    0.05       0  5000.1    0.05       0  5014.2    0.05       0
  5039.8    0.12       0  5274.8    0.05       0  5361.6    0.12       0
  5392.8    0.05       0  5489.0    0.12       0
Bank Sta=5000.1,5014.2
Exp/Cntr=0.3,0.1

Type RM Length L Ch R = 1,5160,585,585,585
BEGIN DESCRIPTION:
BERNST CREEK 10.0
END DESCRIPTION:
XS GIS Cut Line= 3
      2744247.60     10152654.90      2744528.75     10152562.00
      2744905.72     10152103.07
#Sta/Elev= 30
  4703.9 1561.39  4720.1 1561.01  4755.9 1560.38  4784.5 1558.72  4822.1 1558.10
  4885.5 1554.67  4917.3 1552.18  4933.6 1549.89  4975.5 1546.67  4980.7 1544.54
  4986.2 1543.39  4997.0 1542.46  4997.5 1539.46  5010.6 1539.46  5011.1 1542.46
  5011.5 1543.99  5018.4 1544.92  5039.2 1545.11  5061.4 1551.59  5067.9 1551.36
  5096.6 1553.12  5117.4 1553.12  5174.8 1554.93  5253.0 1554.92  5318.5 1556.19
  5438.1 1559.88  5473.3 1562.02  5494.1 1561.94  5565.9 1564.98  5593.9 1565.26
#Mann=7,-1,0
  4703.9    0.12       0  4720.1    0.05       0  4755.9    0.12       0
  4784.5    0.05       0  4997.0    0.05       0  5011.1    0.05       0
  5318.5    0.05       0
Bank Sta=4997,5011.1
Exp/Cntr=0.3,0.1

Type RM Length L Ch R = 1,4575,575,575,575
BEGIN DESCRIPTION:
BERNST CREEK 9.0
END DESCRIPTION:
XS GIS Cut Line= 3
      2744226.74     10152712.17      2744801.75     10152979.00
      2745282.33     10153097.18
#Sta/Elev= 30
  4366.1 1559.03  4410.3 1557.32  4478.0 1556.50  4541.2 1557.72  4643.8 1557.05
  4757.7 1550.27  4849.9 1544.29  4864.4 1544.46  4901.2 1544.63  4929.6 1541.84
  4947.0 1542.64  4952.6 1541.29  4969.9 1542.28  4975.5 1540.23  4992.8 1540.04
  4998.4 1537.88  5007.2 1537.45  5007.7 1534.45  5020.9 1534.45  5021.4 1537.45
  5024.6 1542.62  5039.1 1548.31  5045.2 1549.65  5075.5 1551.47  5135.8 1551.01
  5240.9 1549.76  5258.6 1548.56  5354.2 1550.41  5412.9 1553.15  5494.9 1553.60
#Mann=8,-1,0
  4366.1    0.12       0  4410.3    0.05       0  4757.7    0.12       0
  4864.4    0.05       0  5007.2    0.05       0  5021.4    0.05       0
  5135.8    0.12       0  5258.6    0.05       0
Bank Sta=5007.2,5021.4
Exp/Cntr=0.3,0.1

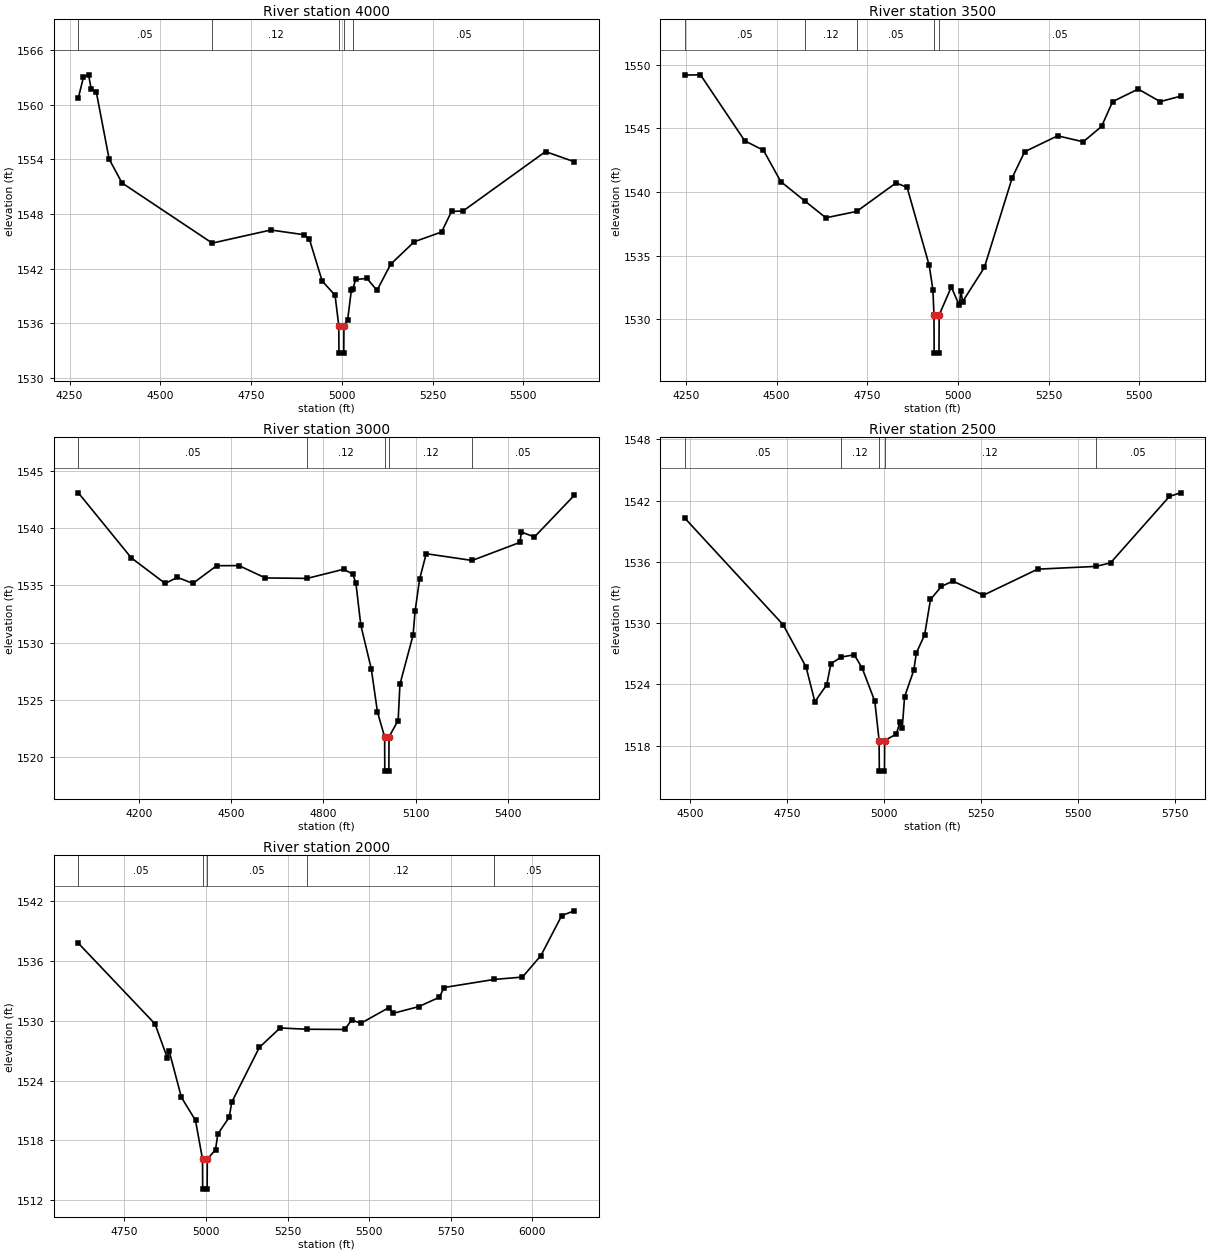
Type RM Length L Ch R = 1,4000,500,500,500
BEGIN DESCRIPTION:
BERNST CREEK 8.0
END DESCRIPTION:
XS GIS Cut Line= 3
      2744005.69     10152853.12      2744512.56     10153372.75
      2745070.56     10153686.17
#Sta/Elev= 30
  4274.1 1560.73  4288.1 1563.00  4302.3 1563.27  4309.5 1561.72  4323.6 1561.38
  4358.9 1554.03  4394.3 1551.40  4643.0 1544.79  4804.5 1546.23  4896.4 1545.71
  4910.5 1545.24  4945.8 1540.63  4981.3 1539.07  4991.6 1535.71  4992.1 1532.71
  5005.3 1532.71  5005.8 1535.71  5015.9 1536.32  5026.1 1539.59  5030.4 1539.77
  5038.0 1540.80  5069.4 1540.91  5096.9 1539.60  5134.5 1542.47  5199.5 1544.94
  5274.8 1546.01  5302.2 1548.27  5334.1 1548.32  5561.1 1554.84  5640.0 1553.73
#Mann=5,-1,0
  4274.1    0.05       0  4643.0    0.12       0  4991.6    0.07       0
  5005.8    0.12       0  5030.4    0.05       0
Bank Sta=4991.6,5005.8
Exp/Cntr=0.3,0.1

Type RM Length L Ch R = 1,3500,500,500,500
BEGIN DESCRIPTION:
BERNST CREEK 7.0
END DESCRIPTION:
XS GIS Cut Line= 3
      2743513.22     10153639.27      2744253.84     10153776.90
      2744861.45     10153863.12
#Sta/Elev= 30
  4246.7 1549.20  4289.9 1549.22  4411.9 1544.03  4463.6 1543.28  4511.3 1540.82
  4576.8 1539.31  4635.7 1537.97  4720.5 1538.47  4829.0 1540.71  4859.5 1540.37
  4920.5 1534.23  4930.7 1532.32  4933.7 1530.32  4934.2 1527.32  4947.5 1527.32
  4948.0 1530.32  4981.5 1532.53  5003.5 1531.07  5007.8 1532.20  5012.8 1531.38
  5072.6 1534.06  5149.6 1541.14  5183.7 1543.17  5274.6 1544.42  5345.3 1543.95
  5395.8 1545.16  5426.1 1547.11  5496.8 1548.10  5557.4 1547.11  5613.7 1547.54
#Mann=5,-1,0
  4246.7    0.05       0  4576.8    0.12       0  4720.5    0.05       0
  4933.7    0.05       0  4948.0    0.05       0
Bank Sta=4933.7,4948
Exp/Cntr=0.3,0.1

Type RM Length L Ch R = 1,3000,500,500,500
BEGIN DESCRIPTION:
BERNST CREEK 6.0
END DESCRIPTION:
XS GIS Cut Line= 3
      2743273.60     10154337.19      2744269.75     10154273.15
      2744846.60     10154055.92
#Sta/Elev= 30
  4001.8 1543.11  4174.2 1537.42  4284.5 1535.18  4324.5 1535.71  4374.6 1535.18
  4452.4 1536.73  4525.0 1536.74  4610.5 1535.66  4747.1 1535.62  4865.7 1536.42
  4895.7 1535.99  4905.7 1535.20  4921.7 1531.52  4955.8 1527.70  4975.9 1523.92
  4999.2 1521.75  4999.7 1518.75  5013.0 1518.75  5013.5 1521.75  5043.2 1523.18
  5049.1 1526.35  5091.8 1530.65  5098.3 1532.73  5113.2 1535.56  5134.6 1537.78
  5284.3 1537.19  5439.5 1538.77  5444.9 1539.67  5487.2 1539.25  5616.4 1542.88
#Mann=5,-1,0
  4001.8    0.05       0  4747.1    0.12       0  4999.2    0.07       0
  5013.5    0.12       0  5284.3    0.05       0
Bank Sta=4999.2,5013.5
Exp/Cntr=0.3,0.1

Type RM Length L Ch R = 1,2500,500,500,500
BEGIN DESCRIPTION:
BERNST CREEK 5.0
END DESCRIPTION:
XS GIS Cut Line= 3
      2743805.71     10154853.11      2744310.72     10154763.50
      2744955.72     10154353.09
#Sta/Elev= 30
  4487.1 1540.29  4740.3 1529.85  4799.4 1525.72  4822.2 1522.30  4852.7 1523.96
  4863.5 1526.03  4890.4 1526.68  4923.8 1526.90  4944.1 1525.59  4976.6 1522.35
  4987.7 1518.50  4988.2 1515.50  5001.5 1515.50  5002.0 1518.50  5032.1 1519.13
  5041.4 1520.31  5047.3 1519.72  5053.3 1522.78  5077.0 1525.38  5083.7 1527.09
  5104.9 1528.84  5120.1 1532.32  5148.1 1533.60  5177.7 1534.12  5256.5 1532.74
  5396.2 1535.29  5546.0 1535.56  5584.1 1535.91  5735.7 1542.42  5764.5 1542.77
#Mann=5,-1,0
  4487.1    0.05       0  4890.4    0.12       0  4987.7    0.07       0
  5002.0    0.12       0  5546.0    0.05       0
Bank Sta=4987.7,5002
Exp/Cntr=0.3,0.1

Type RM Length L Ch R = 1,2000,0,0,0
BEGIN DESCRIPTION:
BERNST CREEK 4.0
END DESCRIPTION:
XS GIS Cut Line= 3
      2743855.71     10155053.13      2744196.58     10155245.08
      2744985.34     10154438.85
#Sta/Elev= 30
  4608.8 1537.79  4843.6 1529.69  4881.2 1526.30  4886.9 1526.99  4924.5 1522.32
  4967.8 1520.00  4989.3 1516.10  4989.8 1513.10  5003.4 1513.10  5003.9 1516.10
  5029.1 1517.06  5036.1 1518.63  5071.5 1520.34  5078.5 1521.81  5163.4 1527.33
  5227.0 1529.28  5309.7 1529.15  5425.0 1529.13  5446.3 1530.08  5474.6 1529.75
  5559.5 1531.31  5573.6 1530.75  5651.3 1531.42  5715.0 1532.36  5729.2 1533.34
  5882.5 1534.15  5969.5 1534.39  6026.1 1536.55  6089.8 1540.56  6127.9 1541.04
#Mann=5,-1,0
  4608.8    0.05       0  4989.3    0.05       0  5003.9    0.05       0
  5309.7    0.12       0  5882.5    0.05       0
Bank Sta=4989.3,5003.9
Exp/Cntr=0.3,0.1

Chan Stop Cuts=-1