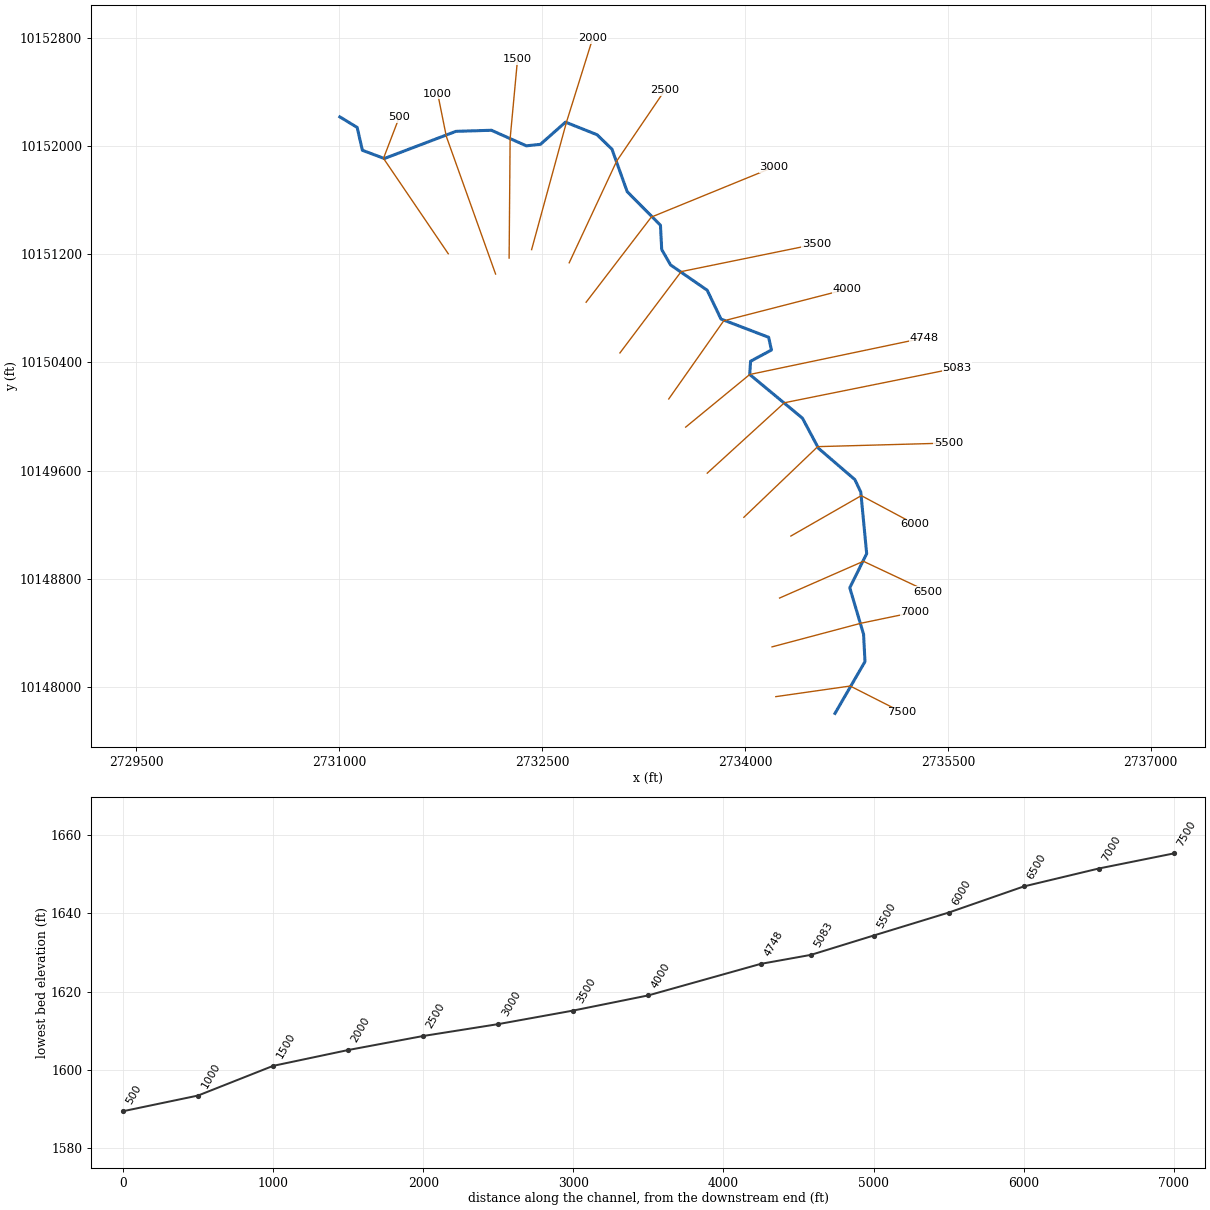
--- BLOCKHOUSE CREEK.prj (project) ---

Proj Title=BLOCKHOUSE CREEK Base Level Engineering
Current Plan=p01
Default Exp/Contr=0.3,0.1
English Units
Geom File=g01
Flow File=f01
Plan File=p01
BEGIN DESCRIPTION:
BLOCKHOUSE CREEK
END DESCRIPTION:

--- BLOCKHOUSE CREEK.p01 (plan) ---

Plan Title=Multiple Run
Short Identifier=Multiple
Geom File=g01
Flow File=f01
Subcritical Flow
K Sum by GR= 0
Std Step Tol= 0.01
Critical Tol= 0.01
Num of Std Step Trials= 20
Max Error Tol= 0.3
Flow Tol Ratio= 0.001
Split Flow NTrial= 30
Split Flow Tol= 0.02
Split Flow Ratio= 0.02
Log Output Level= 0
Friction Slope Method= 1
Unsteady Friction Slope Method= 2
Unsteady Bridges Friction Slope Method= 1
Parabolic Critical Depth
Global Vel Dist=  1 , 1 , 1
Global Log Level= 0
CheckData=True
Encroach Param= -1, 0, 0, 0
BEGIN DESCRIPTION:
Multiple Run
END DESCRIPTION:

--- BLOCKHOUSE CREEK.f01 (steady flow) ---

Flow Title=Multiple
Number of Profiles=7
Profile Names=10-year,25-year,50-year,1pct_min,100-year,1pct_plu,500-year
River Rch & RM= BLOCKHOUSE CREEK,Reach-1,7500
     107     216     346     183     553    1671    1516
Boundary for River Rch & Prof#=BLOCKHOUSE CREEK,Reach-1,1
Up Type=0
Dn Type=3
Dn Slope=0.005
Boundary for River Rch & Prof#=BLOCKHOUSE CREEK,Reach-1,2
Up Type=0
Dn Type=3
Dn Slope=0.005
Boundary for River Rch & Prof#=BLOCKHOUSE CREEK,Reach-1,3
Up Type=0
Dn Type=3
Dn Slope=0.005
Boundary for River Rch & Prof#=BLOCKHOUSE CREEK,Reach-1,4
Up Type=0
Dn Type=3
Dn Slope=0.005
Boundary for River Rch & Prof#=BLOCKHOUSE CREEK,Reach-1,5
Up Type=0
Dn Type=3
Dn Slope=0.005
Boundary for River Rch & Prof#=BLOCKHOUSE CREEK,Reach-1,6
Up Type=0
Dn Type=3
Dn Slope=0.005
Boundary for River Rch & Prof#=BLOCKHOUSE CREEK,Reach-1,7
Up Type=0
Dn Type=3
Dn Slope=0.005

--- BLOCKHOUSE CREEK.g01 (geometry) ---

Geom Title=Existing Conditions

River Reach=BLOCKHOUSE CREEK,Reach-1
Reach XY= 30
      2734665.75     10147804.00      2734887.50     10148187.00
      2734877.00     10148389.00      2734775.00     10148733.00
      2734900.00     10148985.00      2734856.25     10149441.00
      2734812.50     10149533.00      2734543.75     10149764.00
      2734425.00     10149987.00      2734035.25     10150310.00
      2734041.50     10150408.00      2734195.75     10150491.00
      2734175.00     10150585.00      2733822.75     10150720.00
      2733720.75     10150933.00      2733450.00     10151120.00
      2733384.25     10151234.00      2733375.00     10151414.00
      2733129.00     10151662.00      2733016.50     10151976.00
      2732906.25     10152083.00      2732672.75     10152176.00
      2732487.50     10152012.00      2732383.25     10152001.00
      2732125.00     10152116.00      2731862.50     10152108.00
      2731333.25     10151907.00      2731170.75     10151968.00
      2731132.25     10152137.00      2731004.00     10152215.00

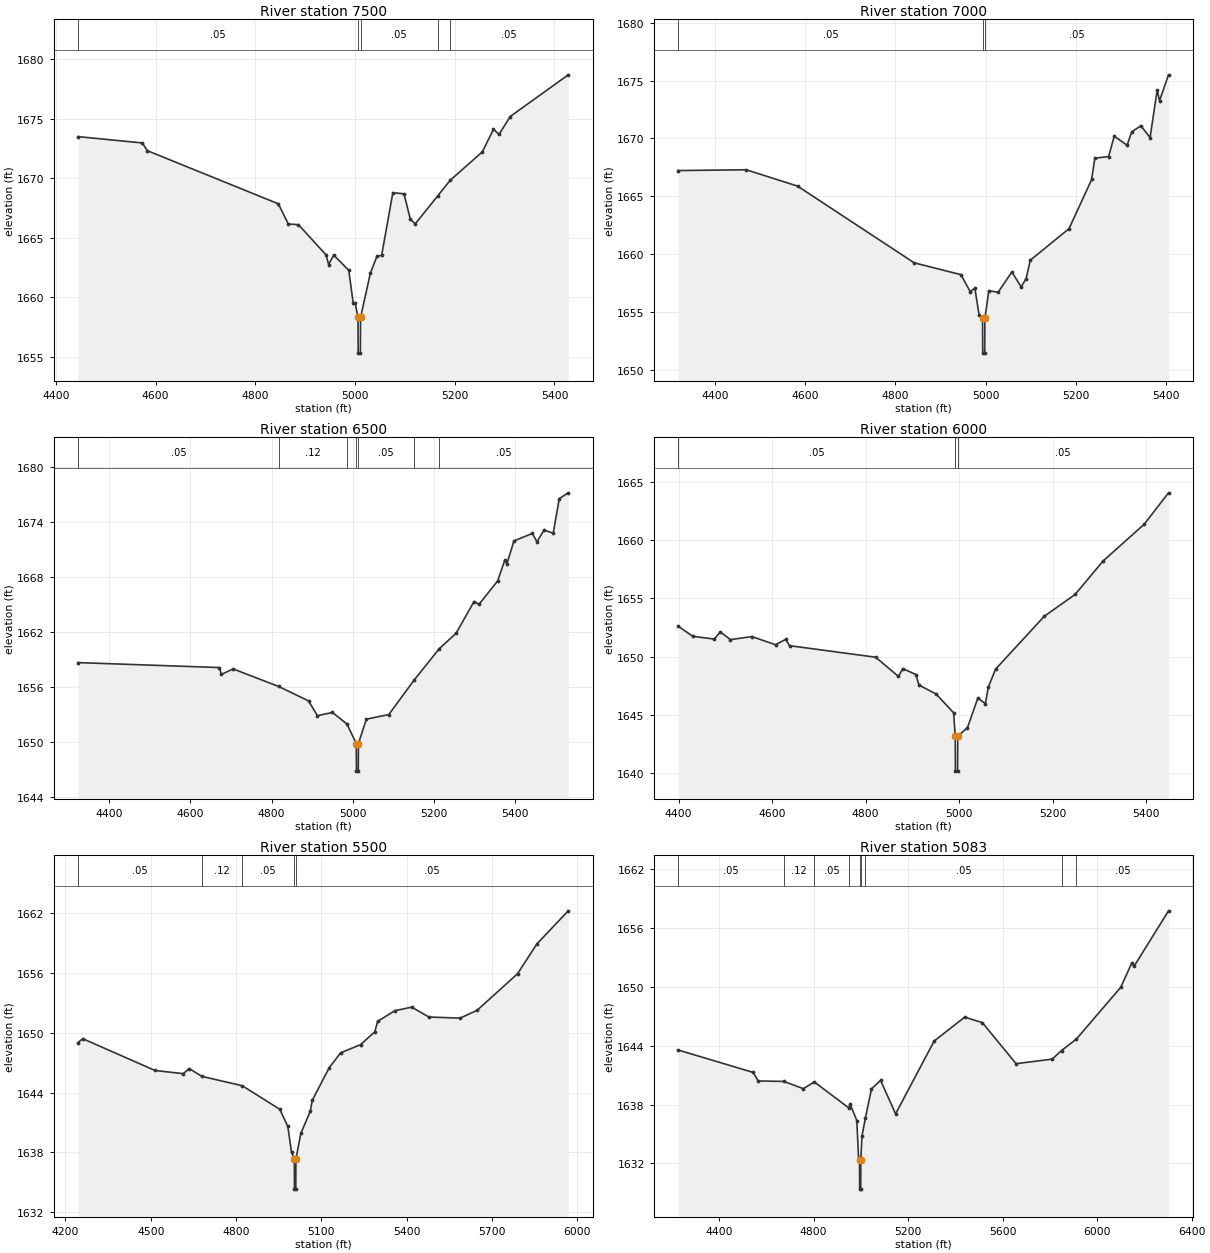
Type RM Length L Ch R = 1,7500,500,500,500
BEGIN DESCRIPTION:
BLOCKHOUSE CREEK 15.0
END DESCRIPTION:
XS GIS Cut Line= 3
      2734228.11     10147927.73      2734778.12     10148006.31
      2735159.48     10147812.90
#Sta/Elev= 30
  4444.4 1673.50  4573.3 1672.97  4583.4 1672.32  4846.0 1667.86  4866.2 1666.16
  4886.4 1666.11  4942.0 1663.56  4947.0 1662.76  4957.1 1663.56  4987.4 1662.27
  4996.2 1659.55  5000.0 1659.55  5005.9 1658.32  5006.3 1655.32  5010.6 1655.32
  5011.0 1658.32  5030.9 1662.06  5044.0 1663.46  5053.3 1663.53  5075.8 1668.79
  5098.2 1668.70  5110.8 1666.58  5120.6 1666.17  5165.7 1668.52  5190.7 1669.83
  5255.2 1672.22  5277.6 1674.11  5288.9 1673.69  5311.2 1675.19  5427.6 1678.69
#Mann=5,-1,0
  4444.4    0.05       0  5005.9    0.03       0  5011.0    0.05       0
  5165.7    0.12       0  5190.7    0.05       0
Bank Sta=5005.9,5011
Exp/Cntr=0.3,0.1

Type RM Length L Ch R = 1,7000,500,500,500
BEGIN DESCRIPTION:
BLOCKHOUSE CREEK 14.0
END DESCRIPTION:
XS GIS Cut Line= 3
      2734200.32     10148295.79      2734858.57     10148470.72
      2735255.71     10148553.12
#Sta/Elev= 30
  4318.9 1667.23  4469.3 1667.30  4583.1 1665.89  4841.8 1659.26  4945.3 1658.24
  4966.0 1656.77  4976.3 1657.07  4985.7 1654.74  4993.3 1654.46  4993.7 1651.46
  4998.1 1651.46  4998.5 1654.46  5007.3 1656.86  5027.7 1656.71  5058.3 1658.47
  5078.8 1657.19  5089.8 1657.88  5099.2 1659.49  5185.0 1662.21  5235.2 1666.46
  5242.2 1668.30  5272.8 1668.44  5285.3 1670.20  5313.7 1669.42  5323.9 1670.57
  5344.3 1671.10  5364.7 1670.08  5380.5 1674.20  5385.6 1673.26  5405.6 1675.50
#Mann=3,-1,0
  4318.9    0.05       0  4993.3    0.05       0  4998.5    0.05       0
Bank Sta=4993.3,4998.5
Exp/Cntr=0.3,0.1

Type RM Length L Ch R = 1,6500,500,500,500
BEGIN DESCRIPTION:
BLOCKHOUSE CREEK 13.0
END DESCRIPTION:
XS GIS Cut Line= 3
      2734255.86     10148656.90      2734875.58     10148928.69
      2735355.72     10148703.09
#Sta/Elev= 30
  4323.3 1658.69  4671.0 1658.15  4676.4 1657.41  4705.3 1658.00  4817.3 1656.09
  4890.9 1654.52  4912.8 1652.91  4949.9 1653.26  4985.5 1652.00  5008.5 1649.87
  5008.9 1646.87  5013.4 1646.87  5013.8 1649.87  5033.3 1652.53  5088.5 1653.03
  5150.8 1656.78  5212.6 1660.19  5254.2 1661.88  5298.4 1665.33  5311.0 1665.05
  5356.6 1667.58  5373.9 1669.81  5379.5 1669.46  5396.7 1671.94  5442.1 1672.76
  5453.4 1671.84  5470.7 1673.12  5493.5 1672.79  5508.4 1676.55  5530.5 1677.18
#Mann=7,-1,0
  4323.3    0.05       0  4817.3    0.12       0  4985.5    0.05       0
  5008.5    0.05       0  5013.8    0.05       0  5150.8    0.12       0
  5212.6    0.05       0
Bank Sta=5008.5,5013.8
Exp/Cntr=0.3,0.1

Type RM Length L Ch R = 1,6000,500,500,500
BEGIN DESCRIPTION:
BLOCKHOUSE CREEK 12.0
END DESCRIPTION:
XS GIS Cut Line= 3
      2734339.22     10149115.25      2734860.25     10149414.20
      2735255.64     10149203.13
#Sta/Elev= 30
  4399.3 1652.61  4430.4 1651.75  4475.9 1651.52  4489.3 1652.12  4510.9 1651.47
  4556.6 1651.73  4607.3 1651.03  4628.8 1651.49  4637.3 1650.95  4821.5 1649.96
  4870.4 1648.31  4879.4 1648.99  4907.8 1648.47  4914.0 1647.58  4951.0 1646.80
  4988.4 1645.19  4991.8 1643.19  4992.2 1640.19  4996.8 1640.19  4997.2 1643.19
  5018.0 1643.92  5040.2 1646.45  5056.3 1645.99  5062.8 1647.42  5078.2 1648.94
  5182.3 1653.47  5248.2 1655.34  5308.4 1658.22  5396.2 1661.37  5448.2 1664.06
#Mann=3,-1,0
  4399.3    0.05       0  4991.8    0.05       0  4997.2    0.05       0
Bank Sta=4991.8,4997.2
Exp/Cntr=0.3,0.1

Type RM Length L Ch R = 1,5500,417,417,417
BEGIN DESCRIPTION:
BLOCKHOUSE CREEK 11.0
END DESCRIPTION:
XS GIS Cut Line= 3
      2733991.96     10149254.11      2734538.05     10149776.48
      2735505.69     10149803.11
#Sta/Elev= 30
  4244.3 1649.01  4260.5 1649.41  4514.9 1646.22  4614.0 1645.90  4635.3 1646.41
  4679.5 1645.63  4821.6 1644.69  4953.6 1642.33  4981.9 1640.61  4994.9 1638.01
  5004.9 1637.32  5005.3 1634.32  5009.9 1634.32  5010.3 1637.32  5027.6 1639.90
  5061.0 1642.14  5067.7 1643.22  5127.7 1646.51  5167.7 1647.99  5237.7 1648.81
  5287.7 1650.10  5297.7 1651.14  5357.8 1652.21  5417.8 1652.57  5477.8 1651.58
  5587.9 1651.47  5647.9 1652.26  5789.6 1655.92  5858.0 1658.92  5968.0 1662.23
#Mann=5,-1,0
  4244.3    0.05       0  4679.5    0.12       0  4821.6    0.05       0
  5004.9    0.05       0  5010.3    0.05       0
Bank Sta=5004.9,5010.3
Exp/Cntr=0.3,0.1

Type RM Length L Ch R = 1,5083,335,335,335
BEGIN DESCRIPTION:
BLOCKHOUSE CREEK 10.0
END DESCRIPTION:
XS GIS Cut Line= 3
      2733721.11     10149580.48      2734291.50     10150101.00
      2735567.95     10150358.20
#Sta/Elev= 30
  4227.8 1643.57  4544.6 1641.29  4565.6 1640.42  4674.5 1640.37  4756.8 1639.63
  4803.1 1640.32  4949.2 1637.67  4954.7 1638.06  4983.1 1636.38  4990.5 1632.55
  4994.6 1632.38  4995.0 1629.38  4999.6 1629.38  5000.0 1632.38  5004.7 1634.77
  5019.2 1636.61  5045.1 1639.61  5083.7 1640.48  5147.1 1637.06  5310.3 1644.49
  5439.4 1646.93  5514.3 1646.37  5657.1 1642.18  5810.1 1642.65  5849.3 1643.52
  5912.4 1644.70  6100.0 1649.98  6145.7 1652.41  6157.0 1652.15  6302.1 1657.78
#Mann=9,-1,0
  4227.8    0.05       0  4674.5    0.12       0  4803.1    0.05       0
  4949.2    0.12       0  4994.6    0.07       0  5000.0    0.12       0
  5019.2    0.05       0  5849.3    0.12       0  5912.4    0.05       0
Bank Sta=4994.6,5000
Exp/Cntr=0.3,0.1

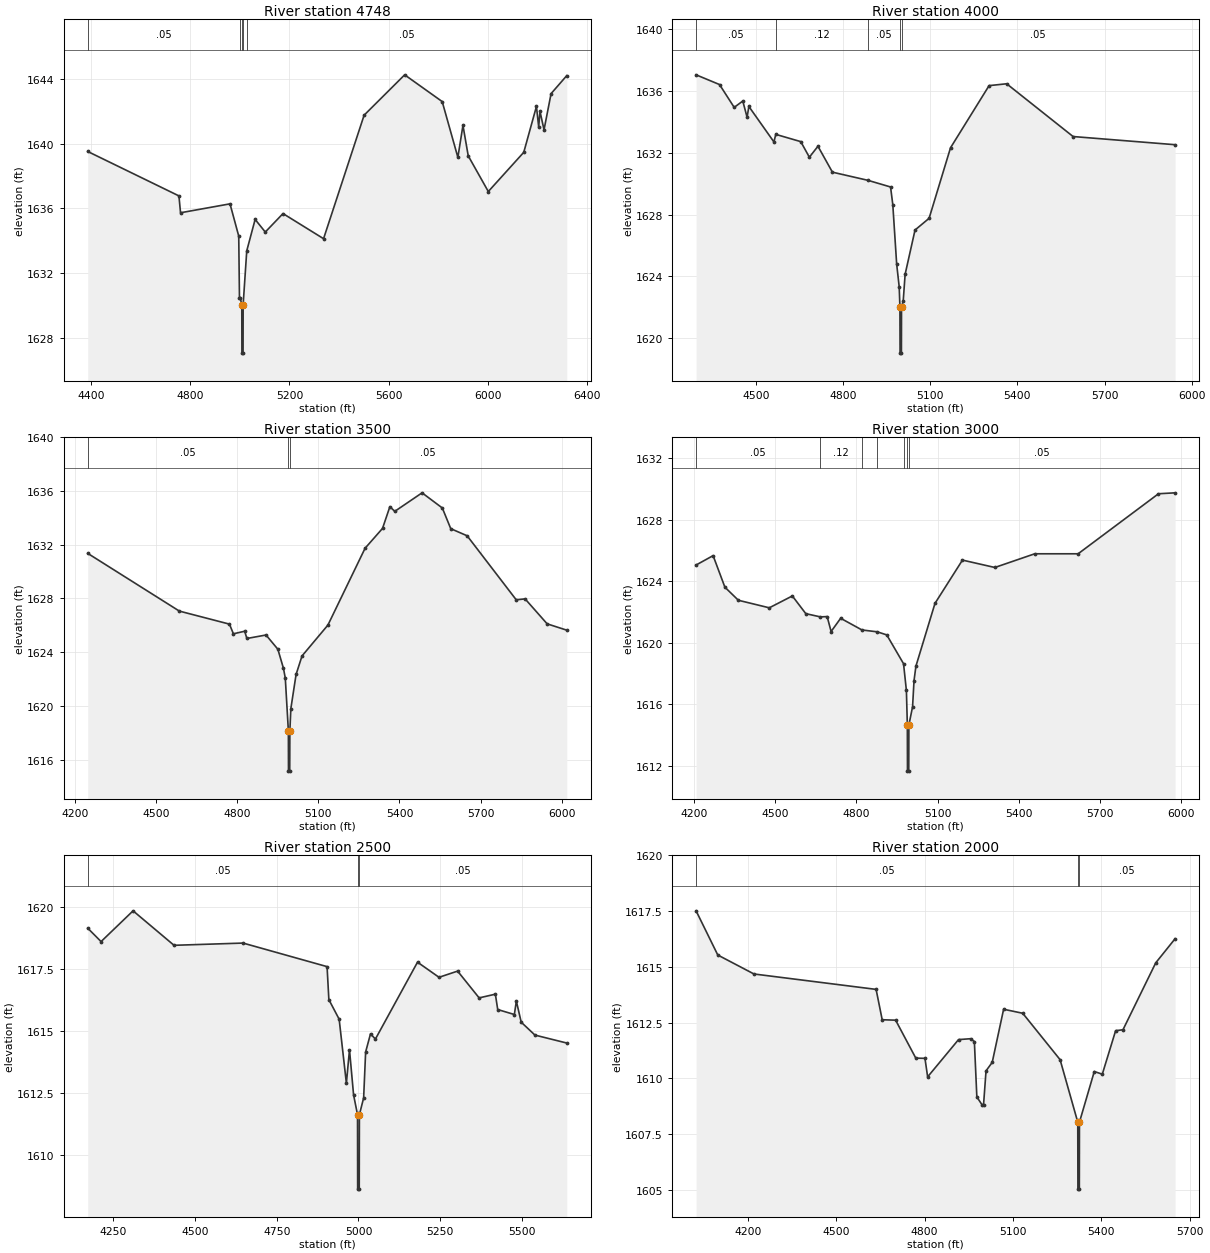
Type RM Length L Ch R = 1,4748,748,748,748
BEGIN DESCRIPTION:
BLOCKHOUSE CREEK 9.0
END DESCRIPTION:
XS GIS Cut Line= 3
      2733561.41     10149920.78      2734035.25     10150310.00
      2735325.29     10150580.50
#Sta/Elev= 30
  4386.8 1639.51  4754.5 1636.77  4760.9 1635.73  4960.4 1636.28  4995.6 1634.29
  4998.5 1630.50  5001.1 1630.50  5007.9 1630.07  5008.4 1627.07  5013.0 1627.07
  5013.4 1630.07  5027.9 1633.38  5061.7 1635.32  5102.6 1634.54  5174.1 1635.68
  5337.6 1634.13  5501.1 1641.75  5664.6 1644.24  5815.9 1642.59  5879.1 1639.15
  5899.6 1641.12  5920.9 1639.24  6001.8 1637.04  6144.8 1639.46  6195.9 1642.29
  6205.0 1641.02  6210.1 1641.99  6226.5 1640.85  6254.9 1643.08  6318.1 1644.19
#Mann=5,-1,0
  4386.8    0.05       0  5001.1    0.12       0  5007.9    0.05       0
  5013.4    0.12       0  5027.9    0.05       0
Bank Sta=5007.9,5013.4
Exp/Cntr=0.3,0.1

Type RM Length L Ch R = 1,4000,500,500,500
BEGIN DESCRIPTION:
BLOCKHOUSE CREEK 8.0
END DESCRIPTION:
XS GIS Cut Line= 3
      2733436.39     10150129.09      2733842.58     10150706.78
      2734755.87     10150941.62
#Sta/Elev= 30
  4293.8 1637.06  4374.5 1636.43  4425.0 1634.95  4454.6 1635.36  4469.4 1634.31
  4475.5 1635.01  4561.8 1632.71  4568.2 1633.20  4654.2 1632.73  4683.8 1631.72
  4713.4 1632.43  4763.2 1630.75  4885.8 1630.22  4963.4 1629.79  4971.1 1628.64
  4984.4 1624.79  4993.1 1623.32  4995.6 1622.02  4996.1 1619.02  5000.7 1619.02
  5001.1 1622.02  5006.9 1622.39  5013.5 1624.13  5047.6 1627.00  5096.1 1627.76
  5169.8 1632.33  5302.6 1636.36  5363.1 1636.48  5591.8 1633.06  5943.0 1632.53
#Mann=5,-1,0
  4293.8    0.05       0  4568.2    0.12       0  4885.8    0.05       0
  4995.6    0.05       0  5001.1    0.05       0
Bank Sta=4995.6,5001.1
Exp/Cntr=0.3,0.1

Type RM Length L Ch R = 1,3500,500,500,500
BEGIN DESCRIPTION:
BLOCKHOUSE CREEK 7.0
END DESCRIPTION:
XS GIS Cut Line= 3
      2733075.29     10150469.38      2733528.43     10151070.90
      2734526.69     10151274.95
#Sta/Elev= 30
  4246.9 1631.36  4585.8 1627.06  4771.1 1626.09  4785.7 1625.37  4827.5 1625.56
  4835.6 1625.02  4906.4 1625.28  4950.2 1624.22  4971.0 1622.79  4977.7 1622.07
  4989.1 1618.14  4989.5 1615.14  4994.1 1615.14  4994.6 1618.14  4998.3 1619.80
  5017.6 1622.34  5039.6 1623.72  5135.4 1626.02  5272.8 1631.74  5337.4 1633.22
  5364.6 1634.84  5382.7 1634.49  5483.7 1635.87  5558.6 1634.74  5589.8 1633.20
  5650.4 1632.67  5832.0 1627.90  5864.8 1627.97  5946.4 1626.11  6018.9 1625.64
#Mann=3,-1,0
  4246.9    0.05       0  4989.1    0.05       0  4994.6    0.05       0
Bank Sta=4989.1,4994.6
Exp/Cntr=0.3,0.1

Type RM Length L Ch R = 1,3000,500,500,500
BEGIN DESCRIPTION:
BLOCKHOUSE CREEK 6.0
END DESCRIPTION:
XS GIS Cut Line= 3
      2732825.32     10150844.41      2733307.32     10151473.86
      2734212.48     10151843.70
#Sta/Elev= 30
  4207.2 1625.06  4270.1 1625.67  4313.7 1623.62  4363.5 1622.77  4477.8 1622.28
  4563.0 1623.05  4612.8 1621.90  4666.7 1621.69  4691.7 1621.71  4706.3 1620.74
  4741.6 1621.60  4820.4 1620.84  4876.9 1620.72  4912.0 1620.52  4974.0 1618.65
  4984.6 1616.91  4988.1 1614.67  4988.6 1611.67  4993.3 1611.67  4993.8 1614.67
  5007.4 1615.85  5012.8 1617.55  5019.8 1618.49  5090.3 1622.57  5191.8 1625.38
  5311.5 1624.90  5459.0 1625.79  5619.4 1625.79  5916.4 1629.69  5977.8 1629.75
#Mann=7,-1,0
  4207.2    0.05       0  4666.7    0.12       0  4820.4    0.05       0
  4876.9    0.12       0  4974.0    0.05       0  4988.1    0.05       0
  4993.8    0.05       0
Bank Sta=4988.1,4993.8
Exp/Cntr=0.3,0.1

Type RM Length L Ch R = 1,2500,500,500,500
BEGIN DESCRIPTION:
BLOCKHOUSE CREEK 5.0
END DESCRIPTION:
XS GIS Cut Line= 3
      2732700.32     10151136.10      2733050.61     10151886.58
      2733408.62     10152413.81
#Sta/Elev= 30
  4171.8 1619.15  4212.6 1618.61  4310.5 1619.85  4435.8 1618.46  4647.0 1618.55
  4904.0 1617.60  4909.5 1616.27  4941.0 1615.48  4963.1 1612.90  4972.6 1614.25
  4985.1 1612.43  4997.2 1611.63  4997.6 1608.63  5002.4 1608.63  5002.9 1611.63
  5015.9 1612.31  5022.0 1614.16  5036.9 1614.89  5051.9 1614.68  5180.7 1617.78
  5246.5 1617.17  5303.4 1617.42  5369.2 1616.34  5418.9 1616.49  5426.1 1615.87
  5477.0 1615.67  5483.1 1616.21  5498.0 1615.36  5540.0 1614.84  5637.3 1614.52
#Mann=3,-1,0
  4171.8    0.05       0  4997.2    0.03       0  5002.9    0.05       0
Bank Sta=4997.2,5002.9
Exp/Cntr=0.3,0.1

Type RM Length L Ch R = 1,2000,500,500,500
BEGIN DESCRIPTION:
BLOCKHOUSE CREEK 4.0
END DESCRIPTION:
XS GIS Cut Line= 3
      2732422.24     10151233.46      2732679.70     10152174.89
      2732873.93     10152795.82
#Sta/Elev= 30
  4024.0 1617.51  4097.7 1615.53  4220.6 1614.68  4635.3 1613.99  4656.0 1612.63
  4701.6 1612.61  4770.1 1610.91  4801.2 1610.90  4810.3 1610.07  4915.2 1611.74
  4956.7 1611.78  4969.0 1611.65  4977.4 1609.17  4996.5 1608.79  5000.0 1608.79
  5008.6 1610.34  5029.6 1610.72  5068.3 1613.10  5133.2 1612.92  5260.1 1610.84
  5320.1 1608.04  5320.6 1605.04  5325.4 1605.04  5325.8 1608.04  5376.2 1610.31
  5403.4 1610.19  5448.7 1612.14  5473.6 1612.18  5584.9 1615.18  5650.6 1616.26
#Mann=3,-1,0
  4024.0    0.05       0  5320.1    0.05       0  5325.8    0.05       0
Bank Sta=5320.1,5325.8
Exp/Cntr=0.3,0.1

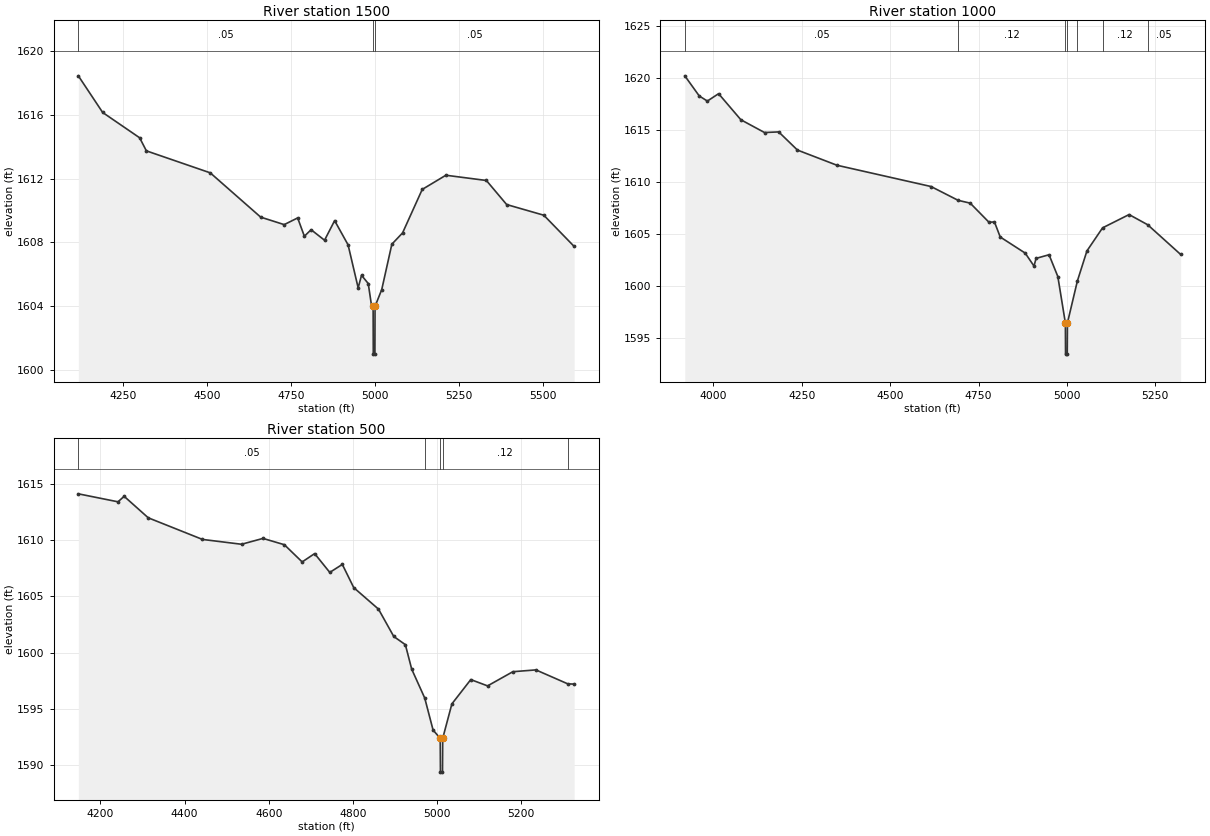
Type RM Length L Ch R = 1,1500,500,500,500
BEGIN DESCRIPTION:
BLOCKHOUSE CREEK 3.0
END DESCRIPTION:
XS GIS Cut Line= 3
      2732255.86     10151170.74      2732263.34     10152052.81
      2732318.36     10152643.05
#Sta/Elev= 30
  4117.9 1618.46  4190.3 1616.16  4300.3 1614.57  4320.3 1613.75  4510.3 1612.37
  4660.3 1609.59  4730.3 1609.12  4770.3 1609.54  4790.3 1608.39  4810.3 1608.80
  4850.3 1608.14  4880.3 1609.37  4920.3 1607.85  4950.3 1605.15  4960.3 1605.94
  4980.3 1605.42  4990.3 1604.00  4994.8 1603.99  4995.3 1600.99  5000.1 1600.99
  5000.5 1603.99  5020.4 1605.04  5050.5 1607.89  5082.4 1608.60  5140.9 1611.33
  5211.2 1612.22  5331.7 1611.89  5392.0 1610.38  5502.5 1609.71  5592.8 1607.75
#Mann=3,-1,0
  4117.9    0.05       0  4994.8    0.05       0  5000.5    0.05       0
Bank Sta=4994.8,5000.5
Exp/Cntr=0.3,0.1

Type RM Length L Ch R = 1,1000,500,500,500
BEGIN DESCRIPTION:
BLOCKHOUSE CREEK 2.0
END DESCRIPTION:
XS GIS Cut Line= 3
      2732155.70     10151053.08      2731791.47     10152070.66
      2731728.08     10152386.05
#Sta/Elev= 30
  3919.2 1620.20  3960.1 1618.26  3983.0 1617.77  4014.8 1618.48  4077.8 1615.97
  4144.7 1614.74  4184.8 1614.80  4237.9 1613.05  4349.5 1611.59  4615.7 1609.54
  4692.4 1608.21  4726.5 1607.94  4779.6 1606.10  4795.1 1606.13  4811.4 1604.68
  4882.0 1603.13  4907.0 1601.88  4912.8 1602.62  4949.5 1602.97  4974.4 1600.87
  4995.7 1596.40  4996.2 1593.40  5001.0 1593.40  5001.5 1596.40  5029.7 1600.45
  5056.7 1603.34  5100.9 1605.56  5175.9 1606.84  5228.5 1605.86  5321.7 1603.00
#Mann=7,-1,0
  3919.2    0.05       0  4692.4    0.12       0  4995.7    0.07       0
  5001.5    0.12       0  5029.7    0.05       0  5100.9    0.12       0
  5228.5    0.05       0
Bank Sta=4995.7,5001.5
Exp/Cntr=0.3,0.1

Type RM Length L Ch R = 1,500,0,0,0
BEGIN DESCRIPTION:
BLOCKHOUSE CREEK 1.0
END DESCRIPTION:
XS GIS Cut Line= 3
      2731805.68     10151203.12      2731326.95     10151908.26
      2731443.36     10152212.45
#Sta/Elev= 30
  4147.7 1614.11  4242.0 1613.40  4256.5 1613.89  4313.8 1611.98  4442.6 1610.06
  4535.5 1609.63  4586.4 1610.15  4637.2 1609.59  4679.5 1608.06  4709.1 1608.80
  4745.1 1607.13  4774.9 1607.84  4802.0 1605.78  4860.8 1603.87  4897.1 1601.44
  4924.7 1600.71  4939.7 1598.54  4970.7 1595.97  4990.5 1593.13  5007.5 1592.39
  5008.0 1589.39  5012.9 1589.39  5013.4 1592.39  5035.2 1595.45  5080.1 1597.61
  5120.0 1597.05  5180.1 1598.31  5234.8 1598.47  5310.6 1597.23  5325.7 1597.21
#Mann=5,-1,0
  4147.7    0.05       0  4970.7    0.12       0  5007.5    0.07       0
  5013.4    0.12       0  5310.6    0.05       0
Bank Sta=5007.5,5013.4
Exp/Cntr=0.3,0.1

Chan Stop Cuts=-1