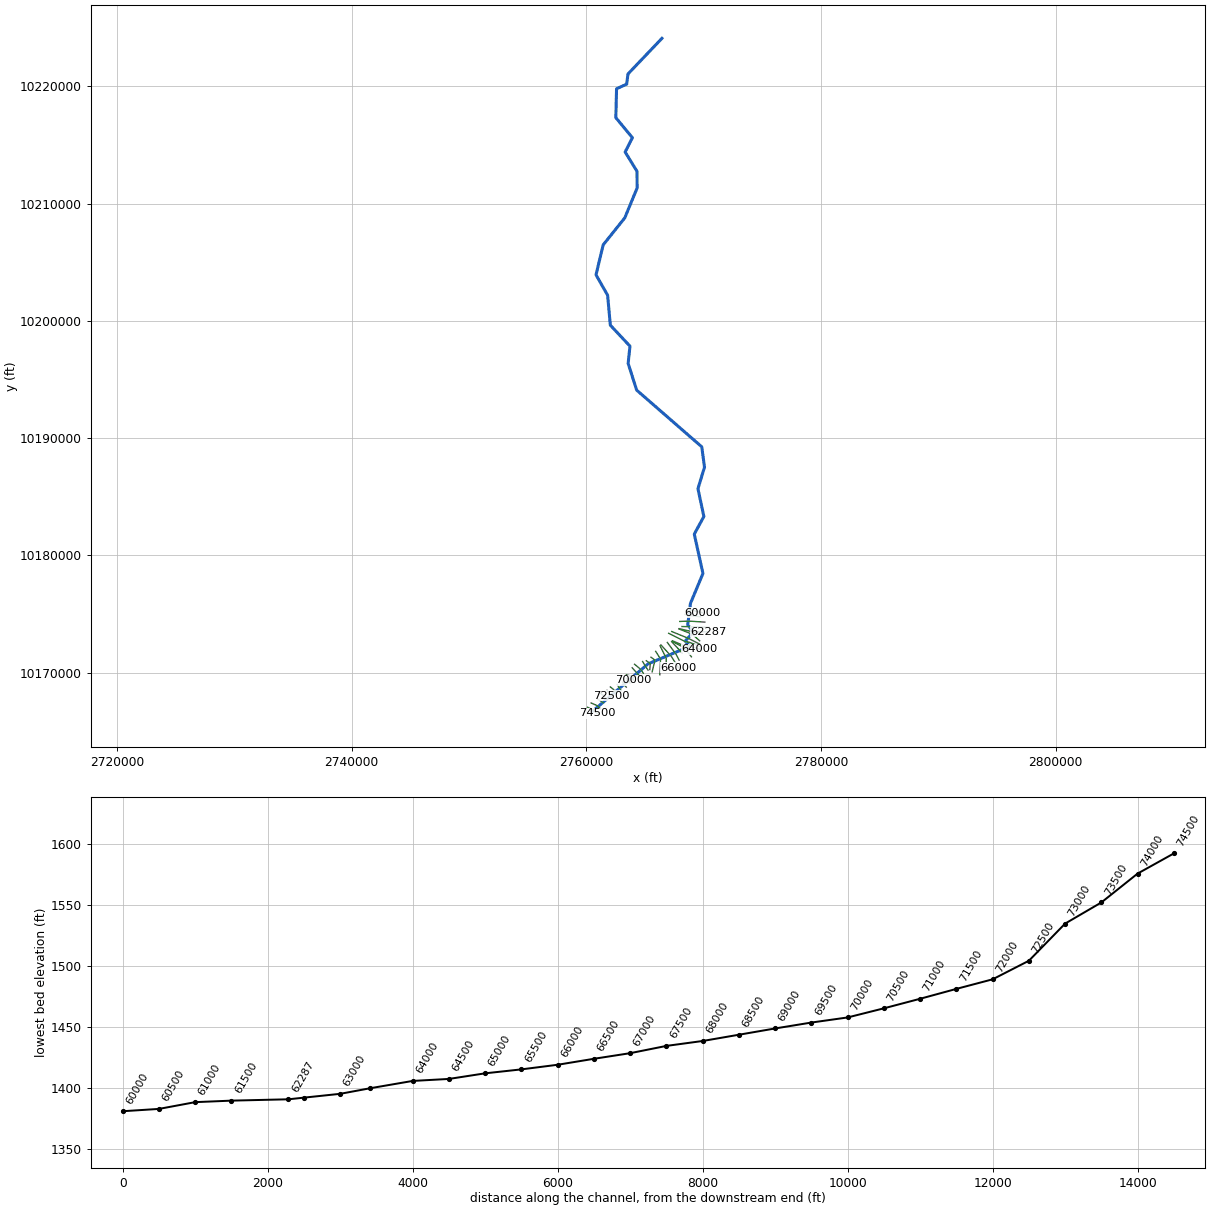
--- BULLHEAD CREEK.prj (project) ---

Proj Title=BULLHEAD CREEK Base Level Engineering
Current Plan=p01
Default Exp/Contr=0.3,0.1
English Units
Geom File=g01
Flow File=f01
Plan File=p01
Y Axis Title=Elevation
X Axis Title(PF)=Main Channel Distance
X Axis Title(XS)=Station
BEGIN DESCRIPTION:
BULLHEAD CREEK
END DESCRIPTION:
DSS Export Rating Curves= 0
DSS Export Rating Curve Sorted= 0
DSS Export Volume Flow Curves= 0
DXF OffsetX= 0
DXF OffsetY= 0
DXF ScaleX= 1
DXF ScaleY= 10

--- BULLHEAD CREEK.p01 (plan) ---

Plan Title=Multiple Run
Short Identifier=Multiple
Geom File=g01
Flow File=f01
Subcritical Flow
K Sum by GR= 0
Std Step Tol= 0.01
Critical Tol= 0.01
Num of Std Step Trials= 20
Max Error Tol= 0.3
Flow Tol Ratio= 0.001
Split Flow NTrial= 30
Split Flow Tol= 0.02
Split Flow Ratio= 0.02
Log Output Level= 0
Friction Slope Method= 1
Unsteady Friction Slope Method= 2
Unsteady Bridges Friction Slope Method= 1
Parabolic Critical Depth
Global Vel Dist=  1 , 1 , 1
Global Log Level= 0
CheckData=True
Encroach Param= -1, 0, 0, 0
BEGIN DESCRIPTION:
Multiple Run
END DESCRIPTION:

--- BULLHEAD CREEK.f01 (steady flow) ---

Flow Title=Multiple
Program Version=4.10
Number of Profiles= 7
Profile Names=10-year,25-year,50-year,1pct_min,100-year,1pct_plu,500-year
River Rch & RM=BULLHEAD CREEK,Reach-1         ,74500
      69     128     199     103     310     936     813
River Rch & RM=BULLHEAD CREEK,Reach-1         ,64500
      89     179     285     150     454    1370    1229
River Rch & RM=BULLHEAD CREEK,Reach-1         ,56000
     117     244     395     211     637    1923    1765
River Rch & RM=BULLHEAD CREEK,Reach-1         ,53500
     134     282     461     247     747    2255    2090
River Rch & RM=BULLHEAD CREEK,Reach-1         ,51500
     165     357     588     318     961    2902    2732
River Rch & RM=BULLHEAD CREEK,Reach-1         ,47500
     259     578     970     533    1610    4862    4708
River Rch & RM=BULLHEAD CREEK,Reach-1         ,44500
     347     789    1338     742    2241    6767    6662
River Rch & RM=BULLHEAD CREEK,Reach-1         ,37000
     348     792    1343     745    2249    6790    6687
River Rch & RM=BULLHEAD CREEK,Reach-1         ,35500
     380     871    1481     823    2486    7508    7429
River Rch & RM=BULLHEAD CREEK,Reach-1         ,34000
     479    1109    1899    1062    3206    9683    9690
River Rch & RM=BULLHEAD CREEK,Reach-1         ,30500
     630    1477    2547    1434    4329   13074   13248
River Rch & RM=BULLHEAD CREEK,Reach-1         ,27000
     648    1522    2626    1479    4467   13490   13686
River Rch & RM=BULLHEAD CREEK,Reach-1         ,22000
     657    1544    2665    1501    4534   13694   13901
River Rch & RM=BULLHEAD CREEK,Reach-1         ,19000
     676    1590    2747    1548    4676   14122   14352
River Rch & RM=BULLHEAD CREEK,Reach-1         ,18500
     690    1626    2811    1585    4788   14458   14708
River Rch & RM=BULLHEAD CREEK,Reach-1         ,13000
     707    1667    2884    1627    4915   14842   15113
River Rch & RM=BULLHEAD CREEK,Reach-1         ,8500
     723    1705    2952    1666    5033   15198   15490
Boundary for River Rch & Prof#=BULLHEAD CREEK,Reach-1         , 1
Up Type= 0
Dn Type= 3
Dn Slope=0.0005
Boundary for River Rch & Prof#=BULLHEAD CREEK,Reach-1         , 2
Up Type= 0
Dn Type= 3
Dn Slope=0.0005
Boundary for River Rch & Prof#=BULLHEAD CREEK,Reach-1         , 3
Up Type= 0
Dn Type= 3
Dn Slope=0.0005
Boundary for River Rch & Prof#=BULLHEAD CREEK,Reach-1         , 4
Up Type= 0
Dn Type= 3
Dn Slope=0.0005
Boundary for River Rch & Prof#=BULLHEAD CREEK,Reach-1         , 5
Up Type= 0
Dn Type= 3
Dn Slope=0.0005
Boundary for River Rch & Prof#=BULLHEAD CREEK,Reach-1         , 6
Up Type= 0
Dn Type= 3
Dn Slope=0.0005
Boundary for River Rch & Prof#=BULLHEAD CREEK,Reach-1         , 7
Up Type= 0
Dn Type= 3
Dn Slope=0.0005
DSS Import GetInterval= 0
DSS Import GetPeak= 0
DSS Import FillOption= 0

--- BULLHEAD CREEK.g01 (geometry) ---

Geom Title=Existing Conditions

River Reach=BULLHEAD CREEK,Reach-1
Reach XY= 30
      2760552.25     10166714.00      2765253.25     10170734.00
      2768808.50     10172227.00      2768429.25     10172683.00
      2769111.50     10173453.00      2768639.00     10174064.00
      2768871.25     10175897.00      2769935.50     10178446.00
      2769196.00     10181805.00      2770013.75     10183305.00
      2769508.00     10185676.00      2770067.25     10187510.00
      2769834.00     10189247.00      2764287.00     10194082.00
      2763560.25     10196362.00      2763715.25     10197834.00
      2762040.75     10199623.00      2761811.00     10202173.00
      2760821.50     10203919.00      2761431.75     10206471.00
      2763273.50     10208775.00      2764323.50     10211319.00
      2764313.25     10212746.00      2763302.75     10214394.00
      2763923.50     10215610.00      2762511.00     10217319.00
      2762571.50     10219787.00      2763434.00     10220177.00
      2763546.50     10221050.00      2766440.25     10224087.00

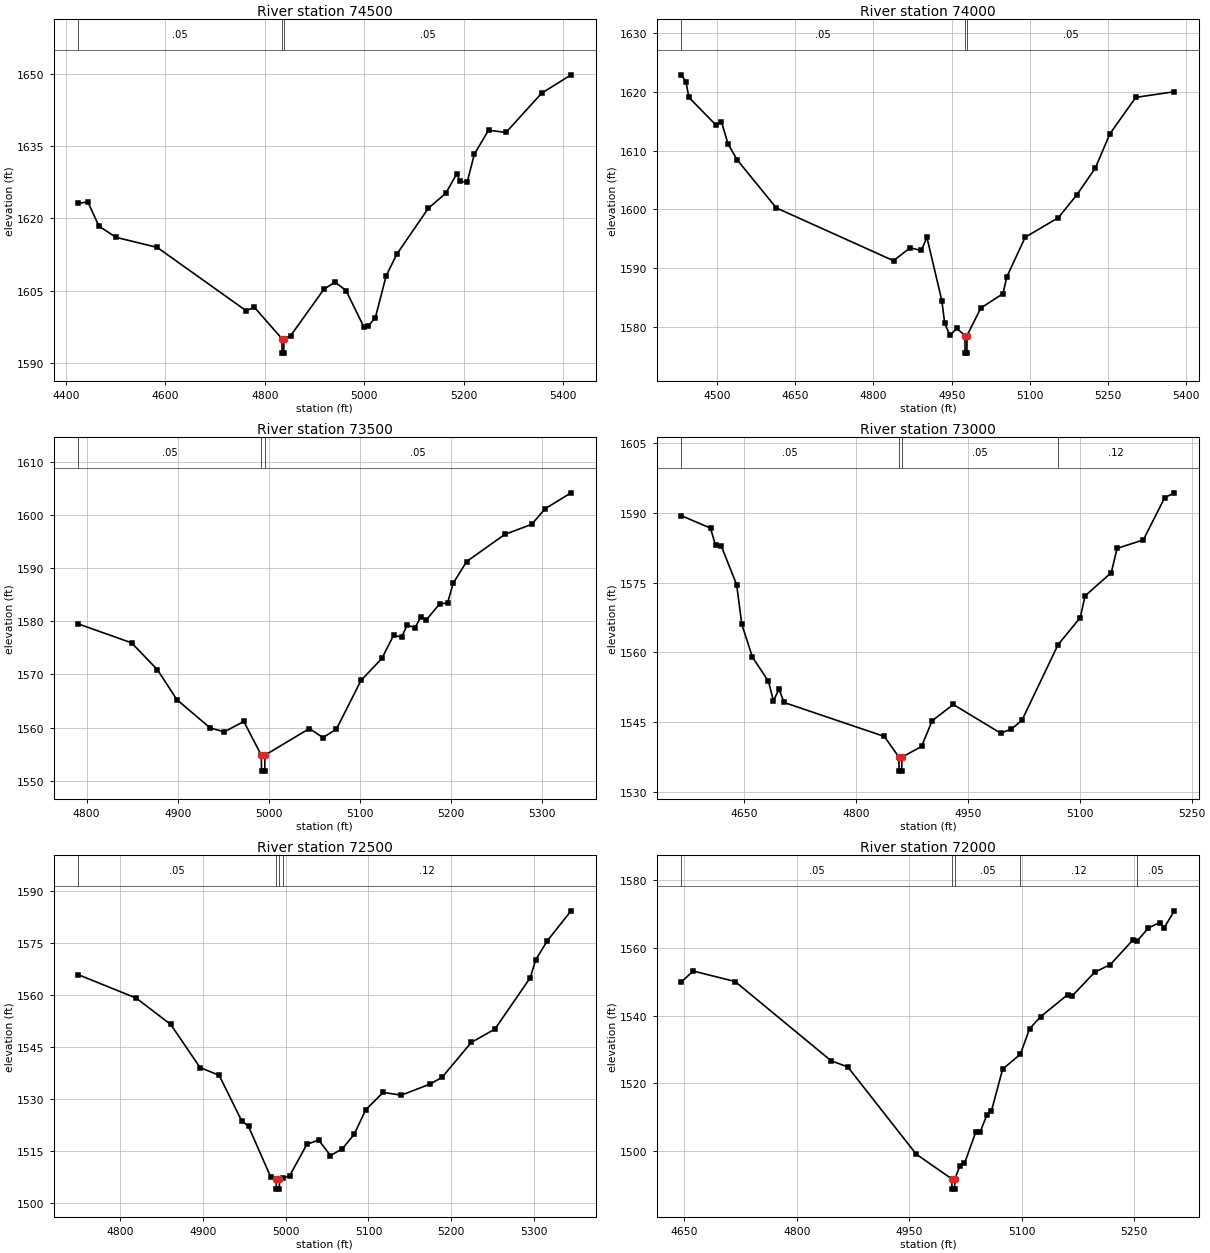
Type RM Length L Ch R = 1,74500,500,500,500
BEGIN DESCRIPTION:
BULLHEAD CREEK 149.0
END DESCRIPTION:
XS GIS Cut Line= 3
      2760097.58     10167038.90      2760612.04     10166780.96
      2760930.79     10166513.81
#Sta/Elev= 30
  4424.5 1623.11  4443.9 1623.40  4466.2 1618.38  4500.7 1616.05  4583.5 1613.96
  4762.2 1600.83  4779.0 1601.52  4834.3 1595.02  4834.5 1592.02  4838.0 1592.02
  4838.3 1595.02  4851.6 1595.60  4918.6 1605.26  4941.0 1606.76  4963.3 1605.01
  4999.2 1597.42  5007.9 1597.66  5022.2 1599.36  5043.9 1608.05  5065.1 1612.52
  5128.8 1622.09  5164.0 1625.21  5186.1 1629.27  5192.6 1627.66  5206.9 1627.50
  5221.2 1633.28  5249.8 1638.28  5285.0 1637.82  5356.5 1645.95  5415.9 1649.78
#Mann=3,-1,0
  4424.5    0.05       0  4834.3    0.05       0  4838.3    0.05       0
Bank Sta=4834.3,4838.3
Exp/Cntr=0.3,0.1

Type RM Length L Ch R = 1,74000,500,500,500
BEGIN DESCRIPTION:
BULLHEAD CREEK 148.0
END DESCRIPTION:
XS GIS Cut Line= 3
      2760405.71     10167403.10      2760924.19     10167170.16
      2761200.01     10166913.01
#Sta/Elev= 30
  4431.6 1622.90  4440.4 1621.67  4445.9 1619.06  4497.7 1614.35  4508.3 1614.93
  4520.9 1611.14  4538.5 1608.42  4613.5 1600.24  4838.4 1591.24  4870.1 1593.43
  4892.0 1592.98  4902.4 1595.24  4931.1 1584.44  4936.6 1580.56  4946.8 1578.54
  4959.7 1579.71  4975.4 1578.50  4975.7 1575.50  4979.2 1575.50  4979.4 1578.50
  5005.9 1583.18  5048.4 1585.63  5055.8 1588.50  5091.0 1595.24  5154.5 1598.56
  5190.1 1602.47  5225.3 1606.99  5253.6 1612.87  5303.0 1619.06  5377.1 1620.02
#Mann=3,-1,0
  4431.6    0.05       0  4975.4    0.05       0  4979.4    0.05       0
Bank Sta=4975.4,4979.4
Exp/Cntr=0.3,0.1

Type RM Length L Ch R = 1,73500,500,500,500
BEGIN DESCRIPTION:
BULLHEAD CREEK 147.0
END DESCRIPTION:
XS GIS Cut Line= 3
      2761005.70     10167703.10      2761184.04     10167593.74
      2761455.72     10167403.09
#Sta/Elev= 30
  4790.8 1579.51  4849.4 1575.94  4877.8 1570.89  4899.1 1565.27  4935.8 1559.93
  4951.3 1559.22  4972.6 1561.17  4991.8 1554.83  4992.1 1551.83  4995.6 1551.83
  4995.8 1554.83  5044.7 1559.84  5059.5 1558.12  5074.3 1559.73  5101.3 1568.88
  5124.2 1573.02  5137.1 1577.38  5145.8 1577.01  5151.9 1579.26  5160.6 1578.81
  5166.7 1580.72  5173.0 1580.27  5187.6 1583.25  5196.3 1583.45  5202.4 1587.12
  5217.2 1591.22  5259.1 1596.32  5288.7 1598.22  5303.5 1601.17  5331.9 1604.14
#Mann=3,-1,0
  4790.8    0.05       0  4991.8    0.03       0  4995.8    0.05       0
Bank Sta=4991.8,4995.8
Exp/Cntr=0.3,0.1

Type RM Length L Ch R = 1,73000,500,500,500
BEGIN DESCRIPTION:
BULLHEAD CREEK 146.0
END DESCRIPTION:
XS GIS Cut Line= 3
      2761226.03     10168228.14      2761547.00     10167935.43
      2761720.76     10167789.83
#Sta/Elev= 30
  4565.6 1589.35  4604.6 1586.69  4611.3 1583.00  4618.8 1582.94  4639.7 1574.51
  4646.5 1566.08  4660.7 1559.02  4682.3 1553.80  4689.0 1549.59  4696.5 1552.11
  4703.2 1549.25  4837.7 1541.95  4857.3 1537.50  4857.5 1534.50  4861.0 1534.50
  4861.3 1537.50  4887.7 1539.80  4901.8 1545.32  4930.2 1548.81  4993.7 1542.66
  5008.1 1543.51  5022.4 1545.45  5070.7 1561.64  5100.5 1567.48  5107.0 1572.14
  5142.1 1577.12  5149.9 1582.34  5185.1 1584.16  5213.7 1593.22  5226.7 1594.27
#Mann=4,-1,0
  4565.6    0.05       0  4857.3    0.05       0  4861.3    0.05       0
  5070.7    0.12       0
Bank Sta=4857.3,4861.3
Exp/Cntr=0.3,0.1

Type RM Length L Ch R = 1,72500,500,500,500
BEGIN DESCRIPTION:
BULLHEAD CREEK 145.0
END DESCRIPTION:
XS GIS Cut Line= 3
      2761755.55     10168479.87      2761905.07     10168278.77
      2762130.76     10168018.22
#Sta/Elev= 30
  4749.4 1565.91  4819.5 1559.14  4861.2 1551.53  4896.6 1539.10  4919.6 1536.88
  4946.7 1523.81  4955.1 1522.13  4982.1 1507.44  4988.5 1507.03  4988.8 1504.03
  4992.3 1504.03  4992.5 1507.03  4996.8 1507.20  5004.7 1507.85  5025.6 1516.96
  5039.8 1518.18  5054.1 1513.73  5068.3 1515.64  5082.6 1519.81  5096.8 1526.95
  5117.7 1531.93  5139.6 1531.14  5174.7 1534.36  5189.0 1536.31  5224.1 1546.35
  5252.6 1550.18  5295.3 1564.98  5302.0 1570.22  5316.2 1575.75  5344.7 1584.32
#Mann=4,-1,0
  4749.4    0.05       0  4988.5    0.07       0  4992.5    0.05       0
  4996.8    0.12       0
Bank Sta=4988.5,4992.5
Exp/Cntr=0.3,0.1

Type RM Length L Ch R = 1,72000,500,500,500
BEGIN DESCRIPTION:
BULLHEAD CREEK 144.0
END DESCRIPTION:
XS GIS Cut Line= 3
      2762042.03     10168770.65      2762318.46     10168549.51
      2762488.86     10168297.87
#Sta/Elev= 30
  4646.0 1549.93  4661.6 1553.15  4717.6 1550.05  4845.7 1526.69  4868.1 1524.84
  4959.3 1499.15  5006.9 1491.82  5007.1 1488.82  5010.6 1488.82  5010.9 1491.82
  5017.8 1495.73  5023.8 1496.40  5038.8 1505.63  5044.8 1505.71  5053.7 1510.73
  5059.8 1511.88  5074.7 1524.21  5098.4 1528.61  5110.7 1536.15  5125.6 1539.71
  5161.6 1546.19  5167.6 1545.80  5197.5 1552.78  5218.5 1555.06  5248.4 1562.26
  5254.3 1562.02  5269.4 1565.87  5284.4 1567.44  5290.4 1565.94  5303.9 1570.90
#Mann=5,-1,0
  4646.0    0.05       0  5006.9    0.05       0  5010.9    0.05       0
  5098.4    0.12       0  5254.3    0.05       0
Bank Sta=5006.9,5010.9
Exp/Cntr=0.3,0.1

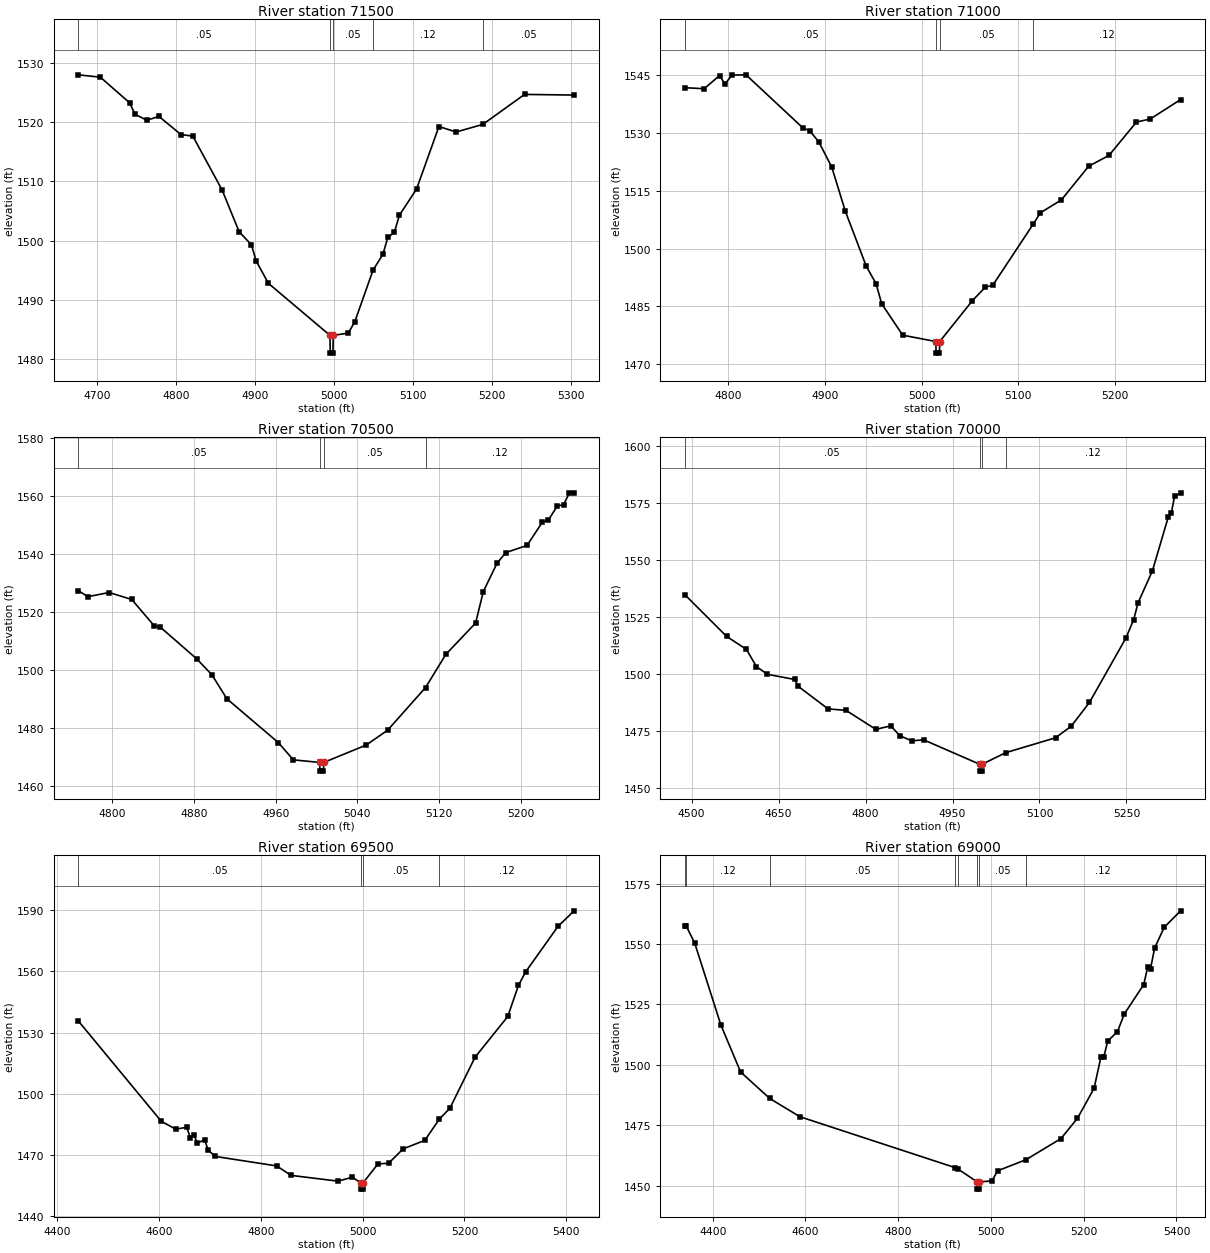
Type RM Length L Ch R = 1,71500,500,500,500
BEGIN DESCRIPTION:
BULLHEAD CREEK 143.0
END DESCRIPTION:
XS GIS Cut Line= 3
      2762627.95     10168974.65      2762792.97     10168696.64
      2762975.19     10168453.80
#Sta/Elev= 30
  4676.7 1528.01  4704.6 1527.61  4741.6 1523.27  4748.3 1521.35  4763.1 1520.34
  4778.7 1520.97  4806.4 1517.92  4821.5 1517.64  4858.6 1508.51  4880.0 1501.48
  4895.6 1499.28  4901.4 1496.58  4917.0 1492.77  4994.9 1483.97  4995.2 1480.97
  4998.7 1480.97  4998.9 1483.97  5018.0 1484.35  5026.3 1486.30  5049.3 1494.99
  5061.8 1497.68  5068.0 1500.54  5076.3 1501.39  5082.6 1504.27  5104.4 1508.72
  5132.6 1519.27  5154.4 1518.35  5188.1 1519.63  5240.9 1524.70  5303.6 1524.59
#Mann=5,-1,0
  4676.7    0.05       0  4994.9    0.05       0  4998.9    0.05       0
  5049.3    0.12       0  5188.1    0.05       0
Bank Sta=4994.9,4998.9
Exp/Cntr=0.3,0.1

Type RM Length L Ch R = 1,71000,500,500,500
BEGIN DESCRIPTION:
BULLHEAD CREEK 142.0
END DESCRIPTION:
XS GIS Cut Line= 3
      2763101.01     10169165.67      2763220.74     10168952.03
      2763400.53     10168753.29
#Sta/Elev= 30
  4755.1 1541.70  4775.1 1541.44  4791.0 1544.83  4796.7 1542.66  4803.9 1544.97
  4818.4 1545.04  4877.8 1531.15  4884.1 1530.60  4893.7 1527.66  4907.1 1521.12
  4921.2 1509.64  4942.8 1495.42  4952.9 1490.90  4958.8 1485.66  4980.5 1477.53
  5014.8 1475.87  5015.0 1472.87  5018.5 1472.87  5018.8 1475.87  5052.5 1486.45
  5066.1 1490.01  5073.6 1490.44  5115.8 1506.43  5122.9 1509.26  5144.6 1512.59
  5172.9 1521.34  5193.9 1524.14  5222.3 1532.80  5236.5 1533.57  5268.0 1538.63
#Mann=4,-1,0
  4755.1    0.05       0  5014.8    0.05       0  5018.8    0.05       0
  5115.8    0.12       0
Bank Sta=5014.8,5018.8
Exp/Cntr=0.3,0.1

Type RM Length L Ch R = 1,70500,500,500,500
BEGIN DESCRIPTION:
BULLHEAD CREEK 141.0
END DESCRIPTION:
XS GIS Cut Line= 3
      2763435.21     10169495.54      2763571.66     10169306.43
      2763717.34     10169100.55
#Sta/Elev= 30
  4766.8 1527.36  4776.1 1525.25  4796.9 1526.70  4819.1 1524.29  4841.1 1515.19
  4847.2 1514.70  4882.8 1503.76  4897.5 1498.33  4912.2 1490.02  4962.5 1474.92
  4977.3 1468.93  5003.1 1468.04  5003.3 1465.04  5006.8 1465.04  5007.1 1468.04
  5048.6 1474.04  5069.5 1479.14  5106.7 1493.89  5126.6 1505.34  5155.7 1516.16
  5163.3 1527.04  5176.6 1536.74  5185.2 1540.46  5206.1 1542.96  5220.9 1550.89
  5227.0 1551.74  5235.7 1556.55  5241.8 1557.02  5247.6 1561.11  5252.2 1561.11
#Mann=4,-1,0
  4766.8    0.05       0  5003.1    0.05       0  5007.1    0.05       0
  5106.7    0.12       0
Bank Sta=5003.1,5007.1
Exp/Cntr=0.3,0.1

Type RM Length L Ch R = 1,70000,500,500,500
BEGIN DESCRIPTION:
BULLHEAD CREEK 140.0
END DESCRIPTION:
XS GIS Cut Line= 3
      2763405.73     10169803.10      2763902.56     10169680.68
      2764005.68     10169353.12
#Sta/Elev= 30
  4488.3 1534.83  4560.4 1516.54  4594.6 1510.88  4611.8 1503.33  4630.9 1499.94
  4677.6 1497.70  4683.9 1494.68  4735.4 1484.80  4766.3 1484.17  4817.8 1475.84
  4843.6 1477.39  4859.0 1473.09  4879.6 1470.83  4900.2 1471.26  4997.0 1460.56
  4997.3 1457.56  5000.8 1457.56  5001.0 1460.56  5041.6 1465.63  5127.7 1472.16
  5154.7 1477.22  5186.2 1487.65  5249.1 1515.86  5262.5 1523.92  5270.0 1531.26
  5294.8 1545.29  5322.0 1568.73  5327.2 1570.44  5332.9 1577.82  5343.4 1579.41
#Mann=4,-1,0
  4488.3    0.05       0  4997.0    0.05       0  5001.0    0.05       0
  5041.6    0.12       0
Bank Sta=4997,5001
Exp/Cntr=0.3,0.1

Type RM Length L Ch R = 1,69500,500,500,500
BEGIN DESCRIPTION:
BULLHEAD CREEK 139.0
END DESCRIPTION:
XS GIS Cut Line= 3
      2763905.65     10170403.15      2764276.47     10169986.19
      2764554.91     10169677.92
#Sta/Elev= 30
  4442.0 1535.69  4604.7 1486.61  4633.1 1482.73  4654.9 1483.63  4661.6 1478.63
  4669.1 1479.69  4675.8 1475.89  4690.0 1477.64  4696.7 1472.49  4710.9 1469.37
  4831.3 1464.74  4859.7 1460.11  4951.7 1457.29  4980.1 1459.21  4996.7 1456.38
  4997.0 1453.38  5000.5 1453.38  5000.7 1456.38  5030.2 1465.71  5051.2 1466.06
  5079.6 1473.08  5122.2 1477.24  5151.0 1487.74  5171.5 1492.99  5220.8 1517.91
  5285.1 1537.88  5306.0 1553.06  5320.2 1559.72  5383.7 1581.97  5415.4 1589.57
#Mann=4,-1,0
  4442.0    0.05       0  4996.7    0.05       0  5000.7    0.05       0
  5151.0    0.12       0
Bank Sta=4996.7,5000.7
Exp/Cntr=0.3,0.1

Type RM Length L Ch R = 1,69000,500,500,500
BEGIN DESCRIPTION:
BULLHEAD CREEK 138.0
END DESCRIPTION:
XS GIS Cut Line= 3
      2764105.69     10170703.11      2764613.89     10170281.69
      2764849.72     10169947.52
#Sta/Elev= 30
  4339.8 1557.43  4342.9 1557.43  4361.3 1550.28  4417.7 1516.40  4460.2 1497.00
  4523.0 1486.06  4587.9 1478.51  4922.2 1457.47  4928.3 1456.95  4970.1 1451.54
  4970.3 1448.54  4973.8 1448.54  4974.1 1451.54  5002.2 1451.92  5014.2 1456.11
  5075.7 1460.74  5150.9 1469.44  5186.6 1477.87  5222.3 1490.23  5237.1 1503.14
  5243.2 1503.18  5251.9 1509.85  5272.8 1513.69  5287.6 1521.03  5329.4 1533.17
  5338.1 1540.52  5344.2 1539.82  5352.9 1548.31  5373.8 1556.94  5409.0 1563.71
#Mann=8,-1,0
  4339.8    0.05       0  4342.9    0.12       0  4523.0    0.05       0
  4922.2    0.12       0  4928.3    0.05       0  4970.1    0.05       0
  4974.1    0.05       0  5075.7    0.12       0
Bank Sta=4970.1,4974.1
Exp/Cntr=0.3,0.1

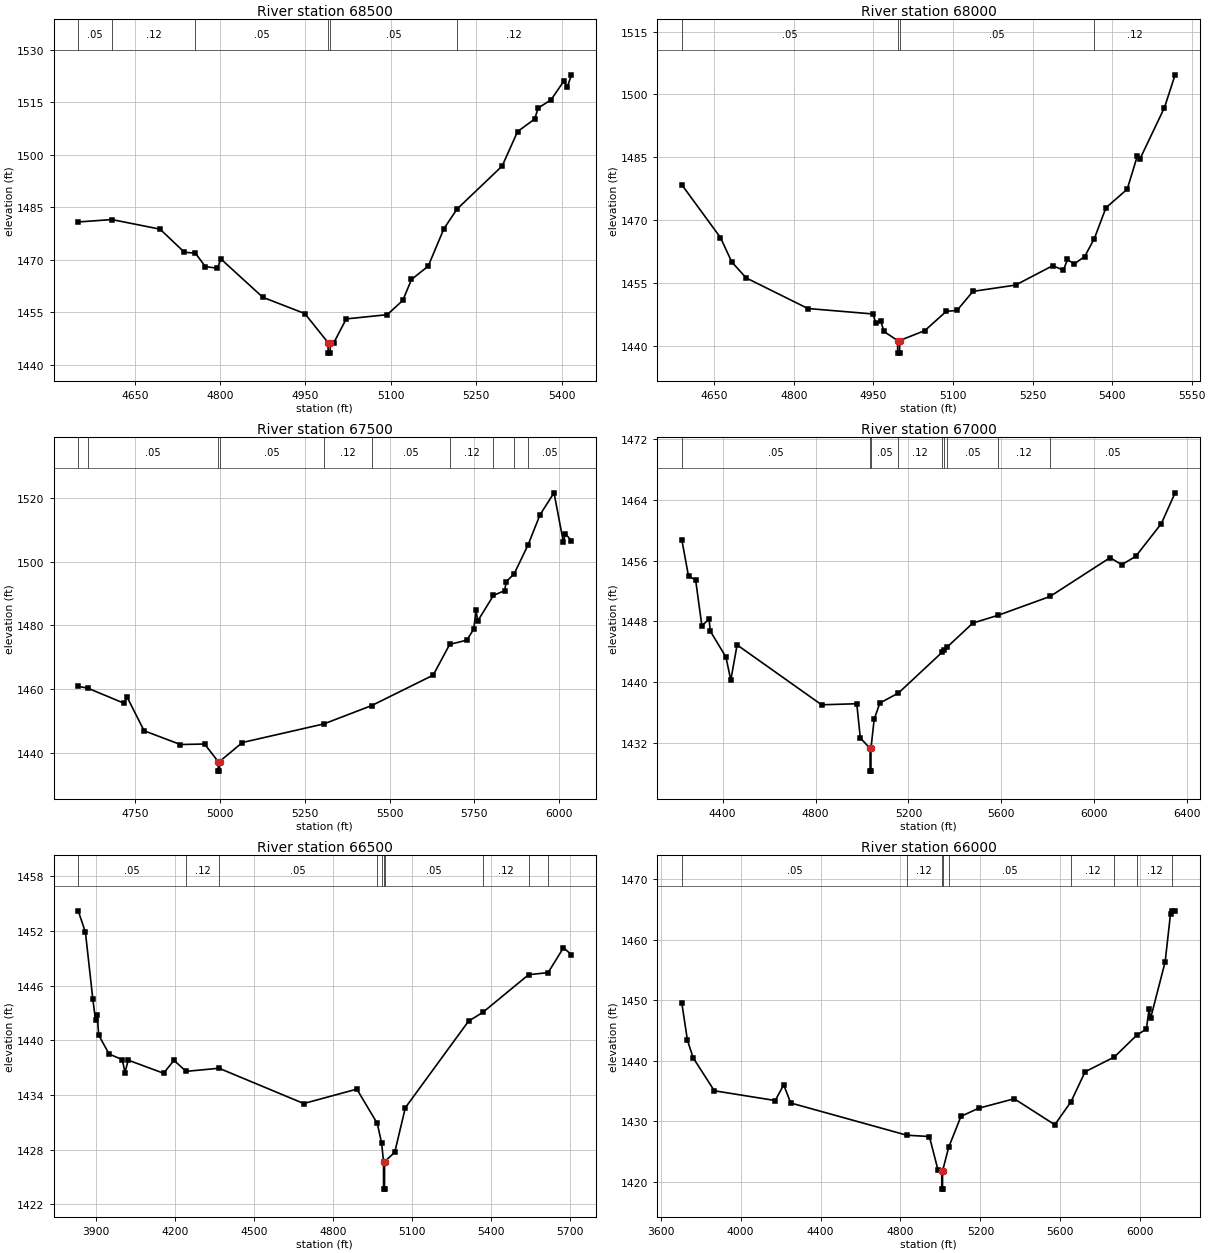
Type RM Length L Ch R = 1,68500,500,500,500
BEGIN DESCRIPTION:
BULLHEAD CREEK 137.0
END DESCRIPTION:
XS GIS Cut Line= 3
      2764793.73     10170936.48      2765025.12     10170551.23
      2765255.66     10170203.15
#Sta/Elev= 30
  4550.6 1480.86  4609.7 1481.55  4694.4 1478.81  4737.1 1472.23  4756.6 1471.94
  4774.0 1468.11  4795.4 1467.64  4801.2 1470.31  4875.1 1459.34  4948.9 1454.69
  4989.7 1446.39  4989.9 1443.39  4993.4 1443.39  4993.7 1446.39  5000.0 1446.42
  5021.7 1453.17  5093.7 1454.37  5121.2 1458.48  5136.3 1464.43  5165.7 1468.24
  5193.4 1478.96  5216.4 1484.55  5295.7 1496.84  5322.8 1506.69  5352.9 1510.28
  5358.9 1513.40  5381.6 1515.76  5404.0 1521.10  5410.0 1519.32  5417.5 1522.90
#Mann=6,-1,0
  4550.6    0.05       0  4609.7    0.12       0  4756.6    0.05       0
  4989.7    0.05       0  4993.7    0.05       0  5216.4    0.12       0
Bank Sta=4989.7,4993.7
Exp/Cntr=0.3,0.1

Type RM Length L Ch R = 1,68000,500,500,500
BEGIN DESCRIPTION:
BULLHEAD CREEK 136.0
END DESCRIPTION:
XS GIS Cut Line= 3
      2765105.65     10171003.13      2765444.57     10170770.45
      2765405.68     10170253.11
#Sta/Elev= 30
  4588.9 1478.44  4661.7 1465.84  4683.0 1460.02  4710.2 1456.21  4826.5 1448.91
  4949.0 1447.61  4955.0 1445.37  4963.9 1445.89  4969.9 1443.43  4995.6 1441.26
  4995.9 1438.26  4999.4 1438.26  4999.6 1441.26  5047.1 1443.65  5087.6 1448.25
  5107.6 1448.44  5137.7 1453.00  5218.0 1454.50  5288.2 1459.14  5308.2 1458.04
  5315.9 1460.63  5328.3 1459.52  5348.3 1461.31  5366.6 1465.62  5388.4 1472.96
  5428.5 1477.38  5447.8 1485.40  5452.9 1484.70  5498.7 1496.86  5518.8 1504.69
#Mann=4,-1,0
  4588.9    0.05       0  4995.6    0.05       0  4999.6    0.05       0
  5366.6    0.12       0
Bank Sta=4995.6,4999.6
Exp/Cntr=0.3,0.1

Type RM Length L Ch R = 1,67500,500,500,500
BEGIN DESCRIPTION:
BULLHEAD CREEK 135.0
END DESCRIPTION:
XS GIS Cut Line= 3
      2765505.67     10171303.12      2765846.30     10171060.86
      2765605.68     10170053.09
#Sta/Elev= 30
  4582.0 1460.85  4610.4 1460.27  4717.3 1455.53  4725.9 1457.51  4776.3 1446.89
  4883.3 1442.58  4954.6 1442.74  4994.6 1437.23  4994.8 1434.23  4998.3 1434.23
  4998.6 1437.23  5065.9 1443.21  5306.2 1449.05  5447.4 1454.82  5628.5 1464.36
  5677.1 1474.02  5727.6 1475.34  5748.2 1478.85  5754.8 1484.71  5759.9 1481.37
  5806.2 1489.39  5838.9 1490.88  5844.1 1493.75  5867.1 1496.14  5908.3 1505.28
  5943.5 1514.72  5984.7 1521.59  6012.5 1506.00  6017.6 1508.76  6036.1 1506.62
#Mann=10,-1,0
  4582.0    0.12       0  4610.4    0.05       0  4994.6    0.05       0
  4998.6    0.05       0  5306.2    0.12       0  5447.4    0.05       0
  5677.1    0.12       0  5806.2    0.05       0  5867.1    0.12       0
  5908.3    0.05       0
Bank Sta=4994.6,4998.6
Exp/Cntr=0.3,0.1

Type RM Length L Ch R = 1,67000,500,500,500
BEGIN DESCRIPTION:
BULLHEAD CREEK 134.0
END DESCRIPTION:
XS GIS Cut Line= 3
      2765905.66     10171803.15      2766323.13     10171149.72
      2766260.75     10169803.67
#Sta/Elev= 30
  4224.6 1458.74  4253.4 1453.94  4283.8 1453.49  4310.9 1447.40  4341.4 1448.32
  4347.3 1446.71  4414.1 1443.31  4435.3 1440.27  4462.4 1444.90  4826.1 1437.01
  4977.5 1437.15  4992.7 1432.64  5034.6 1431.27  5034.9 1428.27  5038.4 1428.27
  5038.6 1431.27  5052.3 1435.10  5076.7 1437.24  5156.8 1438.56  5345.4 1443.95
  5353.9 1444.19  5367.6 1444.65  5477.1 1447.78  5587.4 1448.82  5809.6 1451.29
  6067.8 1456.40  6117.8 1455.47  6177.9 1456.57  6288.0 1460.87  6347.5 1464.94
#Mann=9,-1,0
  4224.6    0.05       0  5034.6    0.05       0  5038.6    0.05       0
  5156.8    0.12       0  5345.4    0.05       0  5353.9    0.12       0
  5367.6    0.05       0  5587.4    0.12       0  5809.6    0.05       0
Bank Sta=5034.6,5038.6
Exp/Cntr=0.3,0.1

Type RM Length L Ch R = 1,66500,500,500,500
BEGIN DESCRIPTION:
BULLHEAD CREEK 133.0
END DESCRIPTION:
XS GIS Cut Line= 3
      2766278.11     10172281.96      2766798.50     10171236.85
      2766811.97     10170532.78
#Sta/Elev= 30
  3832.5 1454.20  3859.9 1451.85  3887.9 1444.53  3898.2 1442.23  3904.7 1442.72
  3910.3 1440.57  3949.5 1438.50  3999.8 1437.87  4010.0 1436.46  4022.2 1437.82
  4156.6 1436.38  4195.8 1437.80  4241.9 1436.59  4367.0 1436.93  4688.3 1433.06
  4889.8 1434.64  4967.5 1430.87  4984.1 1428.68  4991.0 1426.67  4991.3 1423.67
  4994.8 1423.67  4995.0 1426.67  5033.7 1427.72  5073.8 1432.60  5313.8 1442.10
  5368.3 1443.07  5541.4 1447.19  5615.6 1447.42  5673.9 1450.15  5704.2 1449.39
#Mann=10,-1,0
  3832.5    0.05       0  4241.9    0.12       0  4367.0    0.05       0
  4967.5    0.12       0  4984.1    0.05       0  4991.0    0.05       0
  4995.0    0.05       0  5368.3    0.12       0  5541.4    0.05       0
  5615.6    0.12       0
Bank Sta=4991,4995
Exp/Cntr=0.3,0.1

Type RM Length L Ch R = 1,66000,500,500,500
BEGIN DESCRIPTION:
BULLHEAD CREEK 132.0
END DESCRIPTION:
XS GIS Cut Line= 3
      2766355.68     10172353.11      2767225.39     10171394.29
      2767855.68     10170403.12
#Sta/Elev= 30
  3705.5 1449.50  3733.5 1443.37  3761.9 1440.49  3868.0 1435.03  4172.8 1433.42
  4215.4 1436.01  4250.5 1433.01  4831.6 1427.69  4944.6 1427.47  4987.2 1422.01
  5006.6 1421.78  5006.8 1418.78  5010.3 1418.78  5010.6 1421.78  5041.1 1425.68
  5102.6 1430.80  5190.7 1432.14  5369.3 1433.71  5572.5 1429.42  5653.4 1433.22
  5724.3 1438.17  5870.8 1440.62  5984.2 1444.26  6030.7 1445.23  6044.3 1448.48
  6051.8 1446.98  6124.7 1456.32  6151.7 1464.29  6160.3 1464.76  6174.6 1464.74
#Mann=9,-1,0
  3705.5    0.05       0  4831.6    0.12       0  5006.6    0.07       0
  5010.6    0.12       0  5041.1    0.05       0  5653.4    0.12       0
  5870.8    0.05       0  5984.2    0.12       0  6160.3    0.05       0
Bank Sta=5006.6,5010.6
Exp/Cntr=0.3,0.1

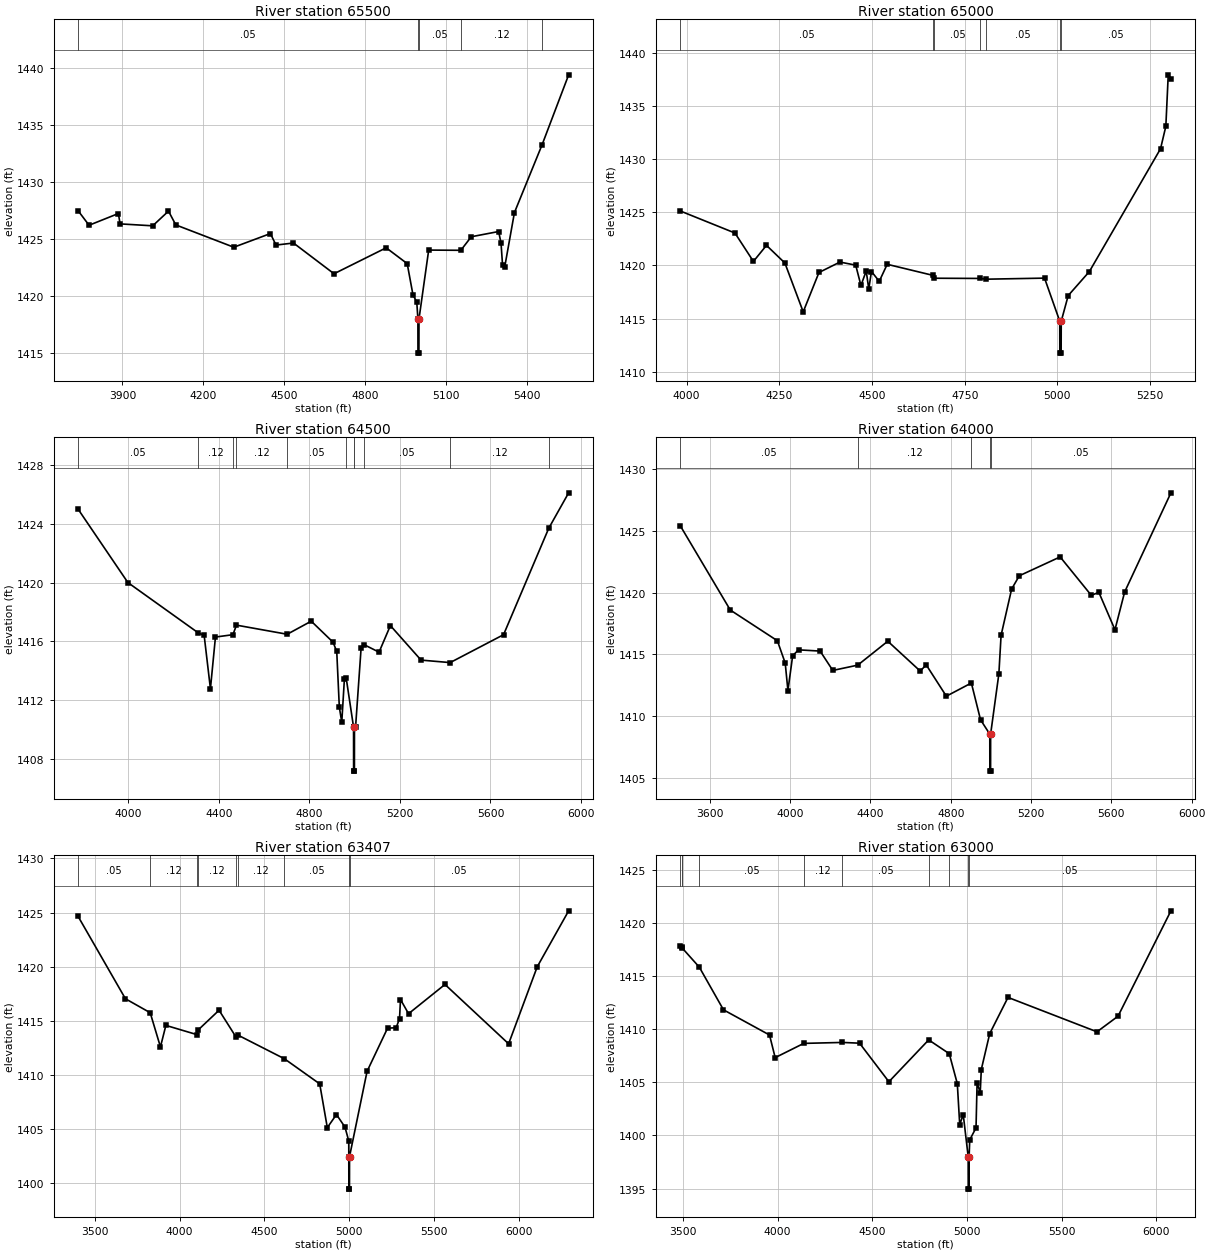
Type RM Length L Ch R = 1,65500,500,500,500
BEGIN DESCRIPTION:
BULLHEAD CREEK 131.0
END DESCRIPTION:
XS GIS Cut Line= 3
      2766898.76     10172564.10      2767647.92     10171545.29
      2767905.69     10171053.10
#Sta/Elev= 30
  3735.4 1427.50  3776.2 1426.22  3885.0 1427.25  3891.2 1426.34  4012.3 1426.17
  4070.9 1427.46  4098.0 1426.25  4313.2 1424.29  4449.0 1425.49  4469.8 1424.48
  4534.6 1424.66  4685.1 1421.96  4878.6 1424.24  4956.6 1422.85  4977.9 1420.12
  4992.1 1419.47  4996.3 1417.99  4996.5 1414.99  5000.0 1414.99  5000.3 1417.99
  5036.3 1424.04  5155.6 1424.02  5194.3 1425.21  5296.0 1425.67  5304.7 1424.64
  5310.3 1422.75  5318.5 1422.57  5354.4 1427.33  5457.4 1433.31  5555.6 1439.43
#Mann=5,-1,0
  3735.4    0.05       0  4996.3    0.05       0  5000.3    0.05       0
  5155.6    0.12       0  5457.4    0.05       0
Bank Sta=4996.3,5000.3
Exp/Cntr=0.3,0.1

Type RM Length L Ch R = 1,65000,500,500,500
BEGIN DESCRIPTION:
BULLHEAD CREEK 130.0
END DESCRIPTION:
XS GIS Cut Line= 3
      2767263.33     10172629.21      2767961.52     10171889.74
      2768155.69     10171653.11
#Sta/Elev= 30
  3983.0 1425.12  4130.3 1423.05  4180.1 1420.38  4215.3 1421.89  4265.0 1420.23
  4314.4 1415.64  4356.9 1419.34  4413.5 1420.32  4456.0 1420.03  4470.1 1418.12
  4484.3 1419.48  4491.2 1417.80  4498.5 1419.43  4519.5 1418.51  4540.9 1420.11
  4664.3 1419.07  4668.2 1418.80  4792.0 1418.78  4807.5 1418.71  4965.3 1418.81
  5006.3 1414.76  5006.5 1411.76  5010.0 1411.76  5010.3 1414.76  5029.1 1417.17
  5086.2 1419.43  5278.1 1430.97  5292.4 1433.08  5298.9 1437.92  5306.1 1437.56
#Mann=7,-1,0
  3983.0    0.05       0  4664.3    0.12       0  4668.2    0.05       0
  4792.0    0.12       0  4807.5    0.05       0  5006.3    0.05       0
  5010.3    0.05       0
Bank Sta=5006.3,5010.3
Exp/Cntr=0.3,0.1

Type RM Length L Ch R = 1,64500,500,500,500
BEGIN DESCRIPTION:
BULLHEAD CREEK 129.0
END DESCRIPTION:
XS GIS Cut Line= 3
      2767300.76     10172657.15      2768386.19     10172094.26
      2768952.17     10171336.74
#Sta/Elev= 30
  3777.3 1425.00  3997.5 1420.00  4308.0 1416.58  4334.6 1416.40  4362.3 1412.77
  4384.5 1416.29  4461.6 1416.45  4477.5 1417.10  4701.6 1416.48  4807.9 1417.37
  4904.2 1415.94  4920.6 1415.31  4932.0 1411.52  4942.8 1410.49  4954.4 1413.42
  4962.3 1413.51  4994.9 1410.16  4995.2 1407.16  4998.7 1407.16  4998.9 1410.16
  5003.8 1410.16  5028.4 1415.57  5042.9 1415.76  5107.6 1415.26  5157.7 1417.07
  5293.2 1414.72  5421.8 1414.55  5657.9 1416.45  5857.7 1423.70  5945.6 1426.11
#Mann=11,-1,0
  3777.3    0.05       0  4308.0    0.12       0  4461.6    0.05       0
  4477.5    0.12       0  4701.6    0.05       0  4962.3    0.12       0
  4994.9    0.07       0  4998.9    0.12       0  5042.9    0.05       0
  5421.8    0.12       0  5857.7    0.05       0
Bank Sta=4994.9,4998.9
Exp/Cntr=0.3,0.1

Type RM Length L Ch R = 1,64000,593,593,593
BEGIN DESCRIPTION:
BULLHEAD CREEK 128.0
END DESCRIPTION:
XS GIS Cut Line= 4
      2767355.25     10172697.20      2768319.24     10172286.14
      2768817.16     10172261.70      2769671.15     10171988.26
#Sta/Elev= 30
  3453.5 1425.42  3702.3 1418.59  3936.7 1416.10  3975.8 1414.29  3989.3 1412.06
  4012.9 1414.88  4042.0 1415.36  4149.7 1415.26  4212.8 1413.69  4337.1 1414.12
  4486.7 1416.06  4648.1 1413.64  4678.1 1414.14  4778.3 1411.60  4902.9 1412.67
  4948.5 1409.69  4994.7 1408.52  4995.0 1405.52  4998.6 1405.52  4998.8 1408.52
  5039.9 1413.42  5050.9 1416.54  5103.4 1420.29  5141.6 1421.37  5345.0 1422.90
  5500.4 1419.78  5537.8 1420.03  5618.0 1416.99  5666.4 1420.06  5896.7 1428.10
#Mann=5,-1,0
  3453.5    0.05       0  4337.1    0.12       0  4902.9    0.05       0
  4994.7    0.05       0  4998.8    0.05       0
Bank Sta=4994.7,4998.8
Exp/Cntr=0.3,0.1

Type RM Length L Ch R = 1,63407,407,407,407
BEGIN DESCRIPTION:
BULLHEAD CREEK 127.0
END DESCRIPTION:
XS GIS Cut Line= 4
      2767013.36     10173344.66      2768440.75     10172626.00
      2768741.95     10172590.87      2769665.15     10172231.57
#Sta/Elev= 30
  3401.9 1424.65  3681.1 1417.04  3827.1 1415.75  3887.5 1412.59  3919.5 1414.58
  4102.2 1413.73  4108.6 1414.14  4233.0 1415.98  4333.6 1413.49  4346.1 1413.67
  4618.1 1411.50  4826.4 1409.18  4871.2 1405.14  4925.1 1406.35  4975.3 1405.19
  4997.6 1403.91  4997.9 1402.46  4998.2 1399.46  5001.8 1399.46  5002.1 1402.46
  5105.6 1410.34  5226.5 1414.33  5276.8 1414.36  5296.9 1415.20  5302.6 1416.97
  5350.2 1415.66  5564.8 1418.36  5940.0 1412.88  6108.6 1419.99  6293.9 1425.16
#Mann=9,-1,0
  3401.9    0.05       0  3827.1    0.12       0  4102.2    0.05       0
  4108.6    0.12       0  4333.6    0.05       0  4346.1    0.12       0
  4618.1    0.05       0  4997.9    0.03       0  5002.1    0.05       0
Bank Sta=4997.9,5002.1
Exp/Cntr=0.3,0.1

Type RM Length L Ch R = 1,63000,500,500,500
BEGIN DESCRIPTION:
BULLHEAD CREEK 126.0
END DESCRIPTION:
XS GIS Cut Line= 3
      2767272.27     10173495.40      2768673.21     10172922.11
      2769631.50     10172432.10
#Sta/Elev= 30
  3486.3 1417.85  3494.2 1417.71  3495.1 1417.67  3586.4 1415.85  3714.1 1411.83
  3957.2 1409.46  3987.0 1407.33  4137.9 1408.67  4341.8 1408.76  4432.5 1408.69
  4587.4 1405.06  4797.5 1409.00  4906.1 1407.70  4948.6 1404.88  4961.3 1401.02
  4979.9 1401.97  5006.4 1397.95  5006.7 1394.95  5010.5 1394.95  5010.8 1397.95
  5014.2 1399.59  5047.4 1400.72  5053.0 1404.96  5069.6 1404.03  5075.2 1406.21
  5119.7 1409.59  5216.2 1413.00  5686.0 1409.76  5797.1 1411.23  6076.3 1421.15
#Mann=10,-1,0
  3486.3    0.12       0  3494.2    0.05       0  3495.1    0.12       0
  3586.4    0.05       0  4137.9    0.12       0  4341.8    0.05       0
  4797.5    0.12       0  4906.1    0.05       0  5006.4    0.05       0
  5010.8    0.05       0
Bank Sta=5006.4,5010.8
Exp/Cntr=0.3,0.1

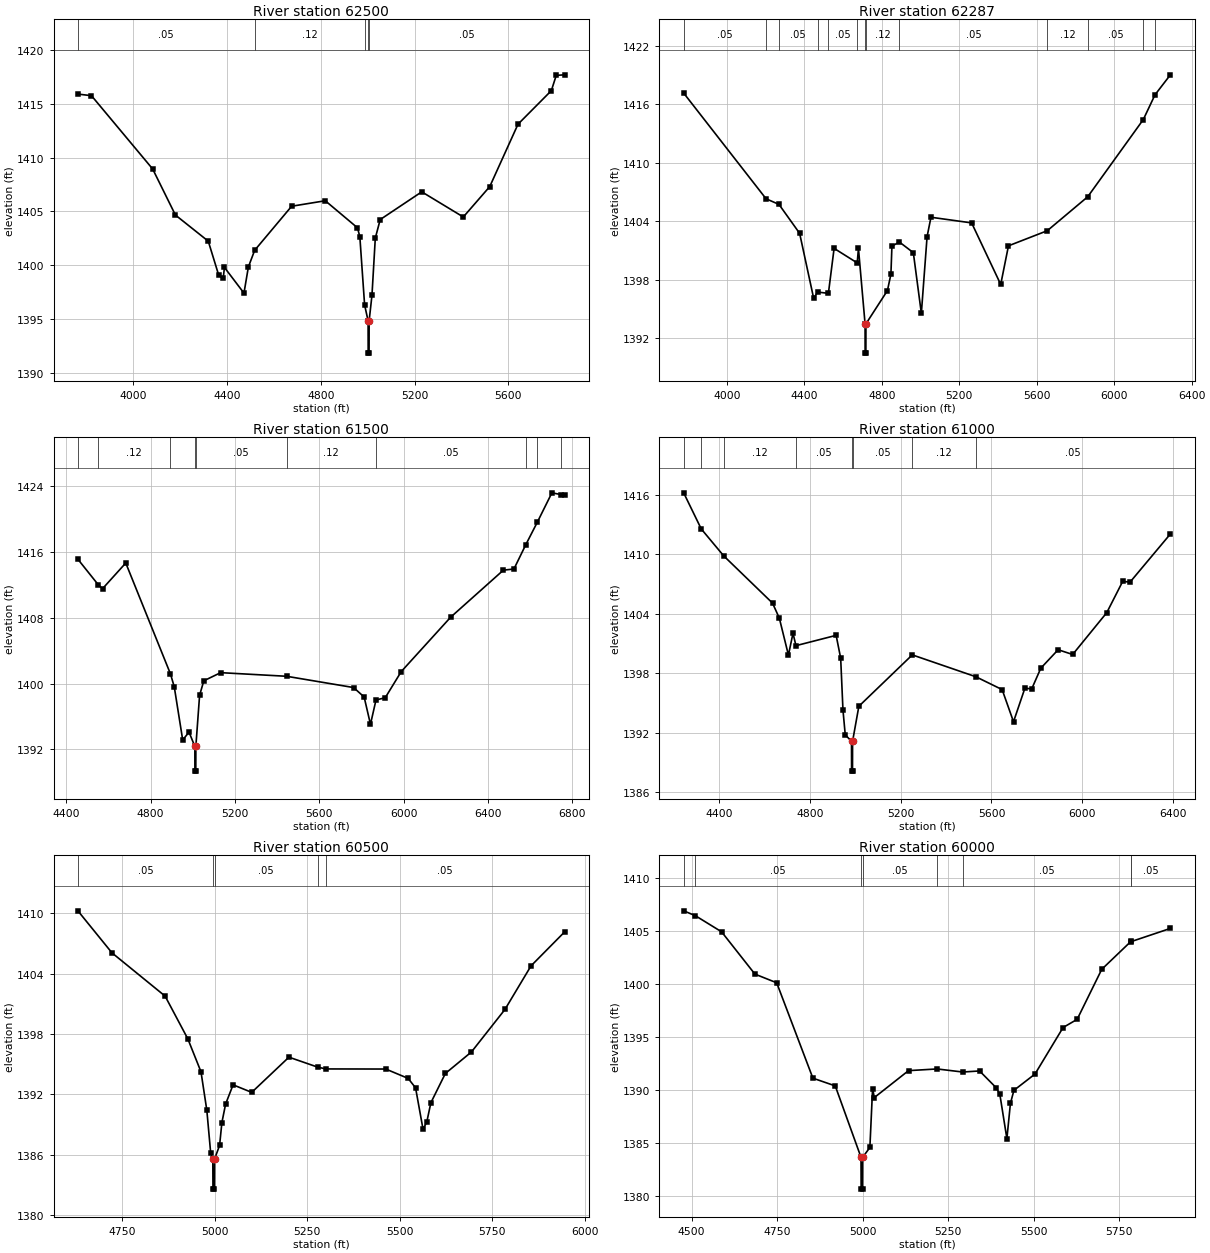
Type RM Length L Ch R = 1,62500,213,213,213
BEGIN DESCRIPTION:
BULLHEAD CREEK 125.0
END DESCRIPTION:
XS GIS Cut Line= 3
      2767879.44     10173720.75      2769027.21     10173259.74
      2769655.66     10172703.13
#Sta/Elev= 30
  3763.1 1415.91  3821.1 1415.76  4082.3 1408.94  4179.3 1404.66  4319.4 1402.23
  4364.2 1399.05  4383.0 1398.76  4388.4 1399.79  4471.7 1397.40  4490.5 1399.83
  4517.3 1401.38  4675.1 1405.48  4818.6 1405.99  4955.7 1403.48  4966.0 1402.66
  4986.4 1396.30  5001.3 1394.82  5001.6 1391.82  5005.4 1391.82  5005.7 1394.82
  5017.8 1397.20  5032.0 1402.51  5052.9 1404.24  5230.2 1406.82  5407.5 1404.48
  5520.4 1407.31  5640.9 1413.11  5783.1 1416.23  5804.0 1417.65  5839.5 1417.70
#Mann=5,-1,0
  3763.1    0.05       0  4517.3    0.12       0  4986.4    0.05       0
  5001.3    0.05       0  5005.7    0.05       0
Bank Sta=5001.3,5005.7
Exp/Cntr=0.3,0.1

Type RM Length L Ch R = 1,62287,787,787,787
BEGIN DESCRIPTION:
BULLHEAD CREEK 124.0
END DESCRIPTION:
XS GIS Cut Line= 3
      2767923.26     10173739.53      2769111.50     10173453.00
      2770401.38     10173476.60
#Sta/Elev= 30
  3777.7 1417.13  4203.1 1406.29  4269.5 1405.72  4376.3 1402.75  4448.8 1396.08
  4468.8 1396.73  4524.8 1396.60  4554.2 1401.21  4673.5 1399.72  4679.9 1401.20
  4714.1 1393.47  4714.4 1390.47  4718.2 1390.47  4718.5 1393.47  4829.4 1396.88
  4847.5 1398.56  4852.7 1401.44  4891.2 1401.86  4963.2 1400.77  5004.6 1394.55
  5034.2 1402.41  5054.2 1404.40  5264.2 1403.82  5414.3 1397.51  5454.3 1401.47
  5654.8 1403.02  5863.5 1406.50  6150.5 1414.42  6210.7 1416.95  6290.1 1419.00
#Mann=13,-1,0
  3777.7    0.05       0  4203.1    0.12       0  4269.5    0.05       0
  4468.8    0.12       0  4524.8    0.05       0  4673.5    0.12       0
  4714.1    0.05       0  4718.5    0.12       0  4891.2    0.05       0
  5654.8    0.12       0  5863.5    0.05       0  6150.5    0.12       0
  6210.7    0.05       0
Bank Sta=4714.1,4718.5
Exp/Cntr=0.3,0.1

Type RM Length L Ch R = 1,61500,500,500,500
BEGIN DESCRIPTION:
BULLHEAD CREEK 123.0
END DESCRIPTION:
XS GIS Cut Line= 3
      2768148.64     10173921.05      2768693.33     10173910.08
      2770455.71     10173853.11
#Sta/Elev= 30
  4455.2 1415.13  4551.1 1412.05  4572.3 1411.55  4682.3 1414.67  4894.4 1401.18
  4912.3 1399.62  4952.3 1393.16  4982.4 1394.11  5010.0 1392.37  5010.4 1389.37
  5014.4 1389.37  5014.7 1392.37  5032.4 1398.58  5052.4 1400.35  5132.4 1401.34
  5444.9 1400.90  5762.8 1399.53  5812.8 1398.38  5842.8 1395.06  5869.0 1398.02
  5912.8 1398.29  5988.7 1401.47  6223.0 1408.08  6473.1 1413.80  6523.2 1413.94
  6578.9 1416.87  6633.9 1419.62  6703.2 1423.20  6747.9 1422.98  6763.3 1422.94
#Mann=10,-1,0
  4455.2    0.05       0  4551.1    0.12       0  4894.4    0.05       0
  5010.0    0.05       0  5014.7    0.05       0  5444.9    0.12       0
  5869.0    0.05       0  6578.9    0.12       0  6633.9    0.05       0
  6747.9    0.12       0
Bank Sta=5010,5014.7
Exp/Cntr=0.3,0.1

Type RM Length L Ch R = 1,61000,500,500,500
BEGIN DESCRIPTION:
BULLHEAD CREEK 122.0
END DESCRIPTION:
XS GIS Cut Line= 3
      2767954.56     10174352.97      2768709.88     10174385.21
      2770095.35     10174296.63
#Sta/Elev= 30
  4244.0 1416.19  4321.4 1412.55  4420.1 1409.84  4635.5 1405.07  4665.5 1403.55
  4705.5 1399.83  4725.6 1402.03  4738.7 1400.78  4915.7 1401.82  4935.7 1399.52
  4945.8 1394.29  4955.8 1391.80  4983.4 1391.13  4983.8 1388.13  4987.8 1388.13
  4988.1 1391.13  5015.8 1394.67  5251.2 1399.85  5530.9 1397.65  5647.1 1396.35
  5697.2 1393.11  5747.3 1396.49  5777.4 1396.42  5817.5 1398.51  5893.8 1400.37
  5957.8 1399.89  6108.1 1404.11  6178.2 1407.26  6210.8 1407.19  6388.3 1412.04
#Mann=8,-1,0
  4244.0    0.12       0  4321.4    0.05       0  4420.1    0.12       0
  4738.7    0.05       0  4983.4    0.05       0  4988.1    0.05       0
  5251.2    0.12       0  5530.9    0.05       0
Bank Sta=4983.4,4988.1
Exp/Cntr=0.3,0.1

Type RM Length L Ch R = 1,60500,500,500,500
BEGIN DESCRIPTION:
BULLHEAD CREEK 121.0
END DESCRIPTION:
XS GIS Cut Line= 3
      2768405.73     10174953.10      2768766.88     10174869.53
      2769705.69     10174753.11
#Sta/Elev= 30
  4629.3 1410.26  4721.6 1406.08  4865.3 1401.78  4926.9 1397.52  4962.4 1394.25
  4978.2 1390.42  4988.5 1386.22  4994.4 1385.59  4994.8 1382.59  4998.9 1382.59
  4999.2 1385.59  5012.7 1386.94  5018.9 1389.21  5029.0 1391.05  5049.2 1392.96
  5099.6 1392.21  5200.3 1395.71  5278.1 1394.72  5300.4 1394.54  5462.3 1394.53
  5522.8 1393.60  5542.9 1392.66  5563.1 1388.54  5573.2 1389.26  5584.3 1391.18
  5623.5 1394.09  5694.1 1396.23  5784.8 1400.46  5855.3 1404.79  5946.0 1408.16
#Mann=5,-1,0
  4629.3    0.05       0  4994.4    0.05       0  4999.2    0.05       0
  5278.1    0.12       0  5300.4    0.05       0
Bank Sta=4994.4,4999.2
Exp/Cntr=0.3,0.1

Type RM Length L Ch R = 1,60000,500,500,500
BEGIN DESCRIPTION:
BULLHEAD CREEK 120.0
END DESCRIPTION:
XS GIS Cut Line= 3
      2768455.70     10175253.11      2768974.97     10175315.41
      2769851.01     10175110.44
#Sta/Elev= 30
  4477.0 1406.94  4511.2 1406.48  4587.8 1404.96  4685.2 1400.97  4748.9 1400.15
  4854.7 1391.15  4920.1 1390.42  4995.4 1383.68  4995.8 1380.68  4999.9 1380.68
  5000.2 1383.68  5021.3 1384.61  5029.2 1390.17  5034.3 1389.32  5134.2 1391.86
  5217.7 1392.02  5292.6 1391.73  5342.0 1391.83  5391.0 1390.23  5401.3 1389.61
  5421.8 1385.44  5432.1 1388.76  5442.3 1390.00  5504.0 1391.54  5586.1 1395.93
  5627.2 1396.70  5699.1 1401.42  5784.3 1404.05  5785.4 1404.04  5899.7 1405.28
#Mann=8,-1,0
  4477.0    0.12       0  4511.2    0.05       0  4995.4    0.05       0
  5000.2    0.05       0  5217.7    0.12       0  5292.6    0.05       0
  5784.3    0.12       0  5785.4    0.05       0
Bank Sta=4995.4,5000.2
Exp/Cntr=0.3,0.1