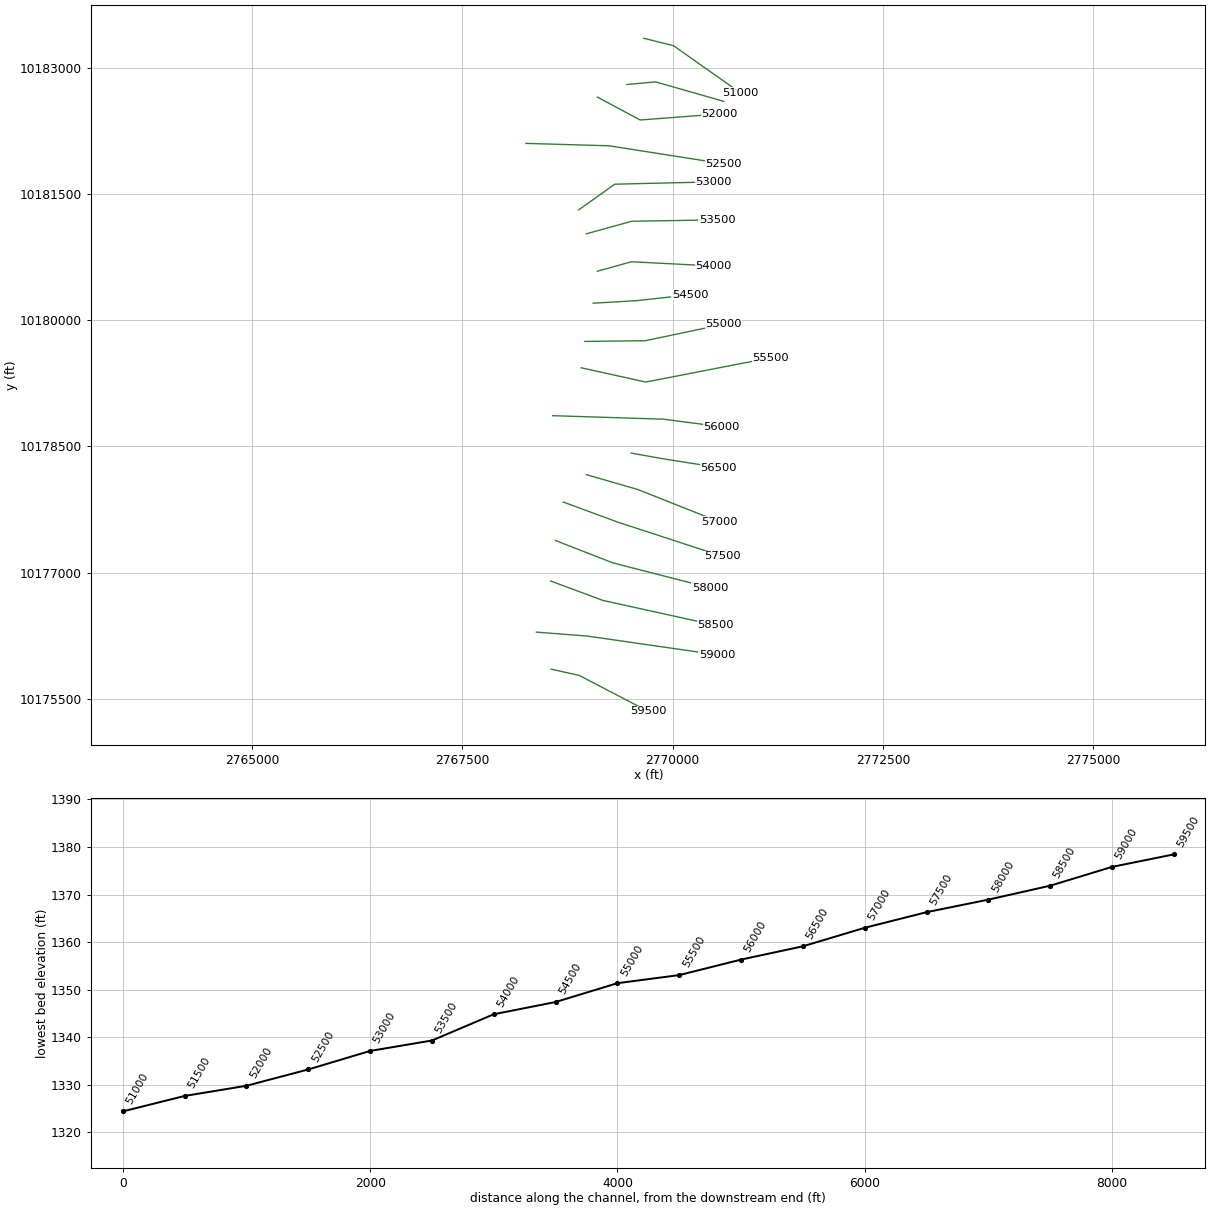
HEC-RAS study BULLHEAD CREEK.prj: BULLHEAD CREEK Base Level Engineering

--- BULLHEAD CREEK.g01 (geometry) --- (continued)

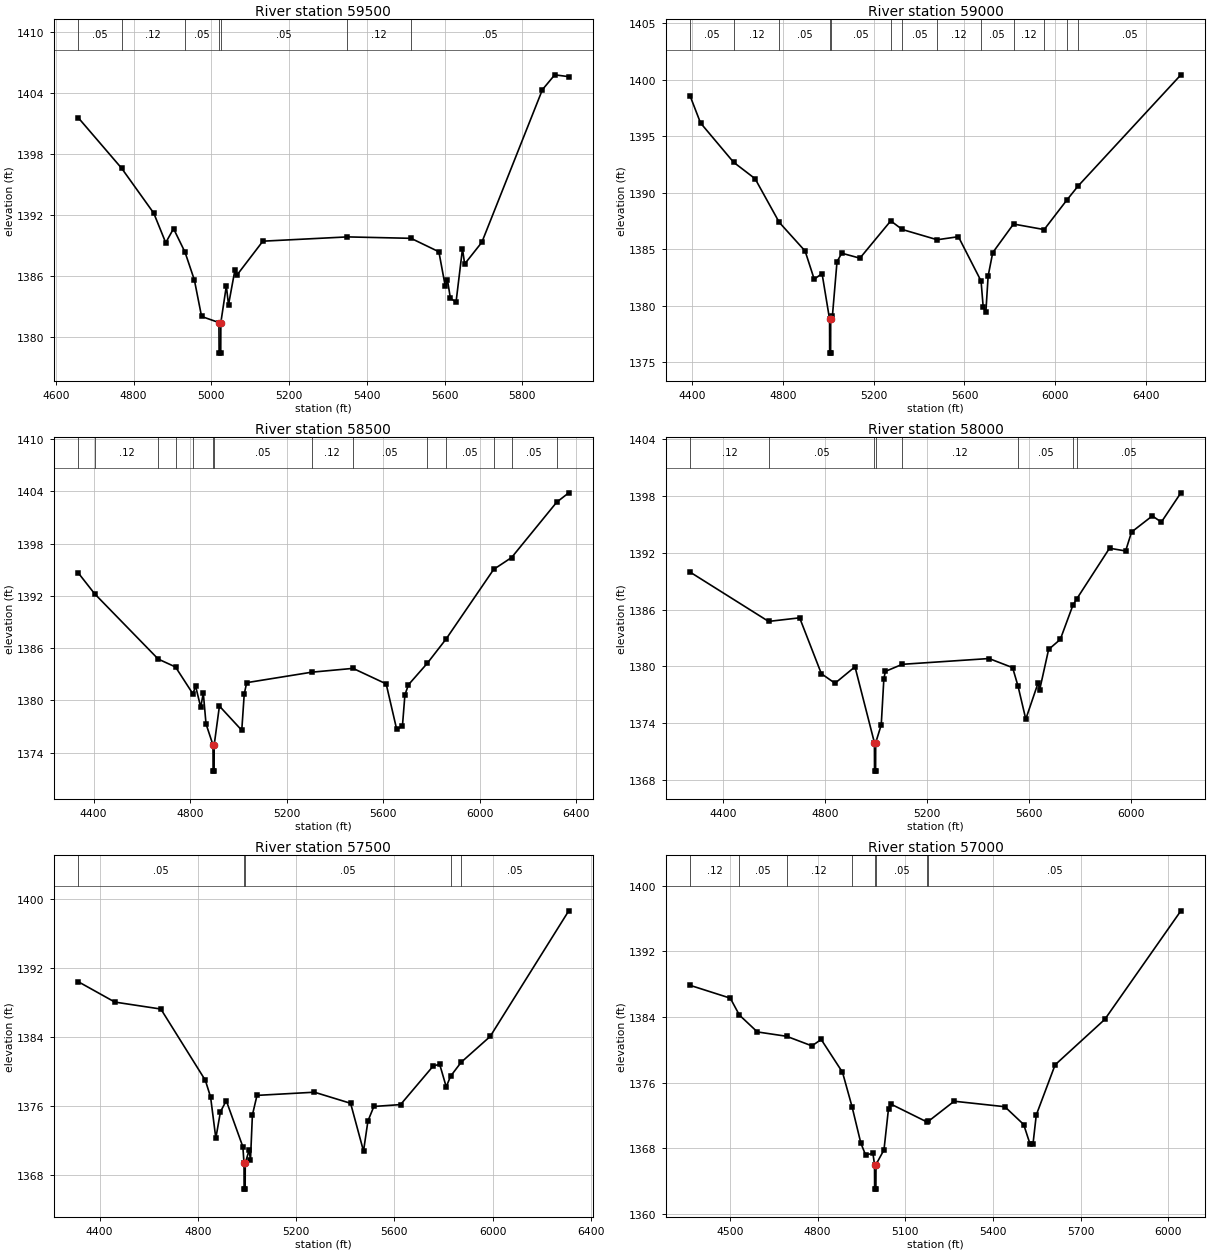
Type RM Length L Ch R = 1,59500,500,500,500
BEGIN DESCRIPTION:
BULLHEAD CREEK 119.0
END DESCRIPTION:
XS GIS Cut Line= 3
      2768555.73     10175853.10      2768890.17     10175777.83
      2769705.70     10175353.11
#Sta/Elev= 30
  4657.2 1401.58  4769.2 1396.60  4851.9 1392.19  4882.7 1389.29  4902.8 1390.67
  4932.3 1388.36  4956.4 1385.63  4974.9 1382.05  5019.6 1381.45  5020.0 1378.45
  5024.2 1378.45  5024.5 1381.45  5038.6 1385.04  5044.2 1383.19  5060.6 1386.59
  5066.3 1386.13  5132.6 1389.44  5350.2 1389.86  5513.7 1389.72  5585.4 1388.40
  5601.9 1385.00  5607.5 1385.62  5615.1 1383.82  5629.6 1383.47  5646.1 1388.69
  5651.7 1387.20  5695.9 1389.33  5851.8 1404.32  5883.5 1405.77  5919.5 1405.59
#Mann=7,-1,0
  4657.2    0.05       0  4769.2    0.12       0  4932.3    0.05       0
  5019.6    0.05       0  5024.5    0.05       0  5350.2    0.12       0
  5513.7    0.05       0
Bank Sta=5019.6,5024.5
Exp/Cntr=0.3,0.1

Type RM Length L Ch R = 1,59000,500,500,500
BEGIN DESCRIPTION:
BULLHEAD CREEK 118.0
END DESCRIPTION:
XS GIS Cut Line= 3
      2768380.23     10176293.46      2768988.37     10176245.86
      2770527.30     10176024.29
#Sta/Elev= 30
  4390.0 1398.55  4435.6 1396.18  4581.2 1392.71  4676.3 1391.25  4782.8 1387.39
  4897.0 1384.85  4937.1 1382.36  4971.7 1382.86  5004.9 1378.82  5005.3 1375.82
  5009.5 1375.82  5009.8 1378.82  5017.5 1379.13  5037.7 1383.91  5058.7 1384.66
  5138.7 1384.22  5274.8 1387.52  5325.2 1386.76  5479.7 1385.85  5573.2 1386.12
  5673.2 1382.20  5682.6 1379.90  5694.4 1379.47  5704.5 1382.65  5724.7 1384.71
  5816.4 1387.24  5951.6 1386.75  6052.0 1389.37  6101.2 1390.60  6554.8 1400.44
#Mann=13,-1,0
  4390.0    0.05       0  4581.2    0.12       0  4782.8    0.05       0
  5004.9    0.05       0  5009.8    0.05       0  5274.8    0.12       0
  5325.2    0.05       0  5479.7    0.12       0  5673.2    0.05       0
  5816.4    0.12       0  5951.6    0.05       0  6052.0    0.12       0
  6101.2    0.05       0
Bank Sta=5004.9,5009.8
Exp/Cntr=0.3,0.1

Type RM Length L Ch R = 1,58500,500,500,500
BEGIN DESCRIPTION:
BULLHEAD CREEK 117.0
END DESCRIPTION:
XS GIS Cut Line= 3
      2768549.20     10176900.66      2769172.32     10176669.82
      2770508.54     10176374.83
#Sta/Elev= 30
  4335.5 1394.66  4404.0 1392.24  4667.5 1384.74  4739.2 1383.83  4811.3 1380.74
  4822.3 1381.64  4843.6 1379.21  4854.3 1380.84  4865.6 1377.29  4894.5 1374.87
  4894.9 1371.87  4899.1 1371.87  4899.4 1374.87  4921.1 1379.34  5013.7 1376.56
  5023.9 1380.73  5034.2 1382.03  5302.9 1383.23  5474.7 1383.67  5611.9 1381.89
  5655.5 1376.67  5679.3 1377.03  5689.6 1380.63  5704.3 1381.79  5781.8 1384.24
  5860.7 1387.06  6057.4 1395.04  6131.6 1396.40  6318.7 1402.76  6368.4 1403.83
#Mann=14,-1,0
  4335.5    0.05       0  4404.0    0.12       0  4667.5    0.05       0
  4739.2    0.12       0  4811.3    0.05       0  4894.5    0.05       0
  4899.4    0.05       0  5302.9    0.12       0  5474.7    0.05       0
  5781.8    0.12       0  5860.7    0.05       0  6057.4    0.12       0
  6131.6    0.05       0  6318.7    0.12       0
Bank Sta=4894.5,4899.4
Exp/Cntr=0.3,0.1

Type RM Length L Ch R = 1,58000,500,500,500
BEGIN DESCRIPTION:
BULLHEAD CREEK 116.0
END DESCRIPTION:
XS GIS Cut Line= 3
      2768605.63     10177382.62      2769286.13     10177117.28
      2770445.95     10176819.26
#Sta/Elev= 30
  4269.6 1389.95  4577.6 1384.75  4699.6 1385.13  4784.9 1379.23  4838.5 1378.22
  4917.1 1379.96  4993.4 1371.94  4993.8 1368.94  4998.0 1368.94  4998.4 1371.94
  5020.2 1373.83  5030.5 1378.69  5036.3 1379.47  5102.8 1380.22  5443.7 1380.83
  5536.4 1379.87  5557.7 1377.91  5588.1 1374.43  5637.0 1378.29  5642.2 1377.47
  5677.8 1381.79  5723.7 1382.85  5773.5 1386.48  5787.9 1387.11  5917.1 1392.48
  5980.4 1392.19  6003.7 1394.19  6085.2 1395.89  6120.8 1395.24  6197.5 1398.33
#Mann=8,-1,0
  4269.6    0.12       0  4577.6    0.05       0  4993.4    0.05       0
  4998.4    0.05       0  5102.8    0.12       0  5557.7    0.05       0
  5773.5    0.12       0  5787.9    0.05       0
Bank Sta=4993.4,4998.4
Exp/Cntr=0.3,0.1

Type RM Length L Ch R = 1,57500,500,500,500
BEGIN DESCRIPTION:
BULLHEAD CREEK 115.0
END DESCRIPTION:
XS GIS Cut Line= 3
      2768699.50     10177839.58      2769344.64     10177601.71
      2770589.86     10177194.85
#Sta/Elev= 30
  4312.4 1390.43  4462.0 1388.05  4649.4 1387.24  4830.6 1378.95  4851.9 1377.00
  4873.2 1372.22  4892.0 1375.30  4915.8 1376.58  4983.3 1371.22  4988.0 1369.30
  4988.3 1366.30  4992.6 1366.30  4993.0 1369.30  5009.0 1370.87  5014.2 1369.65
  5022.1 1374.92  5040.8 1377.20  5274.6 1377.57  5421.9 1376.28  5474.5 1370.72
  5492.4 1374.22  5516.6 1375.91  5625.2 1376.13  5758.6 1380.63  5784.6 1380.81
  5811.2 1378.19  5828.7 1379.42  5871.9 1381.05  5990.0 1384.05  6310.0 1398.66
#Mann=5,-1,0
  4312.4    0.05       0  4988.0    0.05       0  4993.0    0.05       0
  5828.7    0.12       0  5871.9    0.05       0
Bank Sta=4988,4993
Exp/Cntr=0.3,0.1

Type RM Length L Ch R = 1,57000,500,500,500
BEGIN DESCRIPTION:
BULLHEAD CREEK 114.0
END DESCRIPTION:
XS GIS Cut Line= 3
      2768974.89     10178165.09      2769586.15     10177988.33
      2770555.72     10177603.10
#Sta/Elev= 30
  4363.7 1387.87  4500.9 1386.31  4532.0 1384.25  4593.5 1382.19  4693.7 1381.66
  4780.3 1380.49  4812.1 1381.27  4885.0 1377.27  4917.6 1373.08  4947.5 1368.67
  4963.9 1367.19  4989.1 1367.38  4994.6 1366.02  4995.0 1363.02  4999.3 1363.02
  4999.7 1366.02  5027.0 1367.81  5042.5 1372.84  5051.3 1373.38  5175.9 1371.18
  5179.3 1371.30  5267.3 1373.74  5440.7 1373.07  5505.2 1370.90  5526.8 1368.54
  5537.2 1368.56  5548.3 1372.06  5612.8 1378.18  5782.8 1383.72  6043.3 1396.96
#Mann=8,-1,0
  4363.7    0.12       0  4532.0    0.05       0  4693.7    0.12       0
  4917.6    0.05       0  4994.6    0.03       0  4999.7    0.05       0
  5175.9    0.12       0  5179.3    0.05       0
Bank Sta=4994.6,4999.7
Exp/Cntr=0.3,0.1

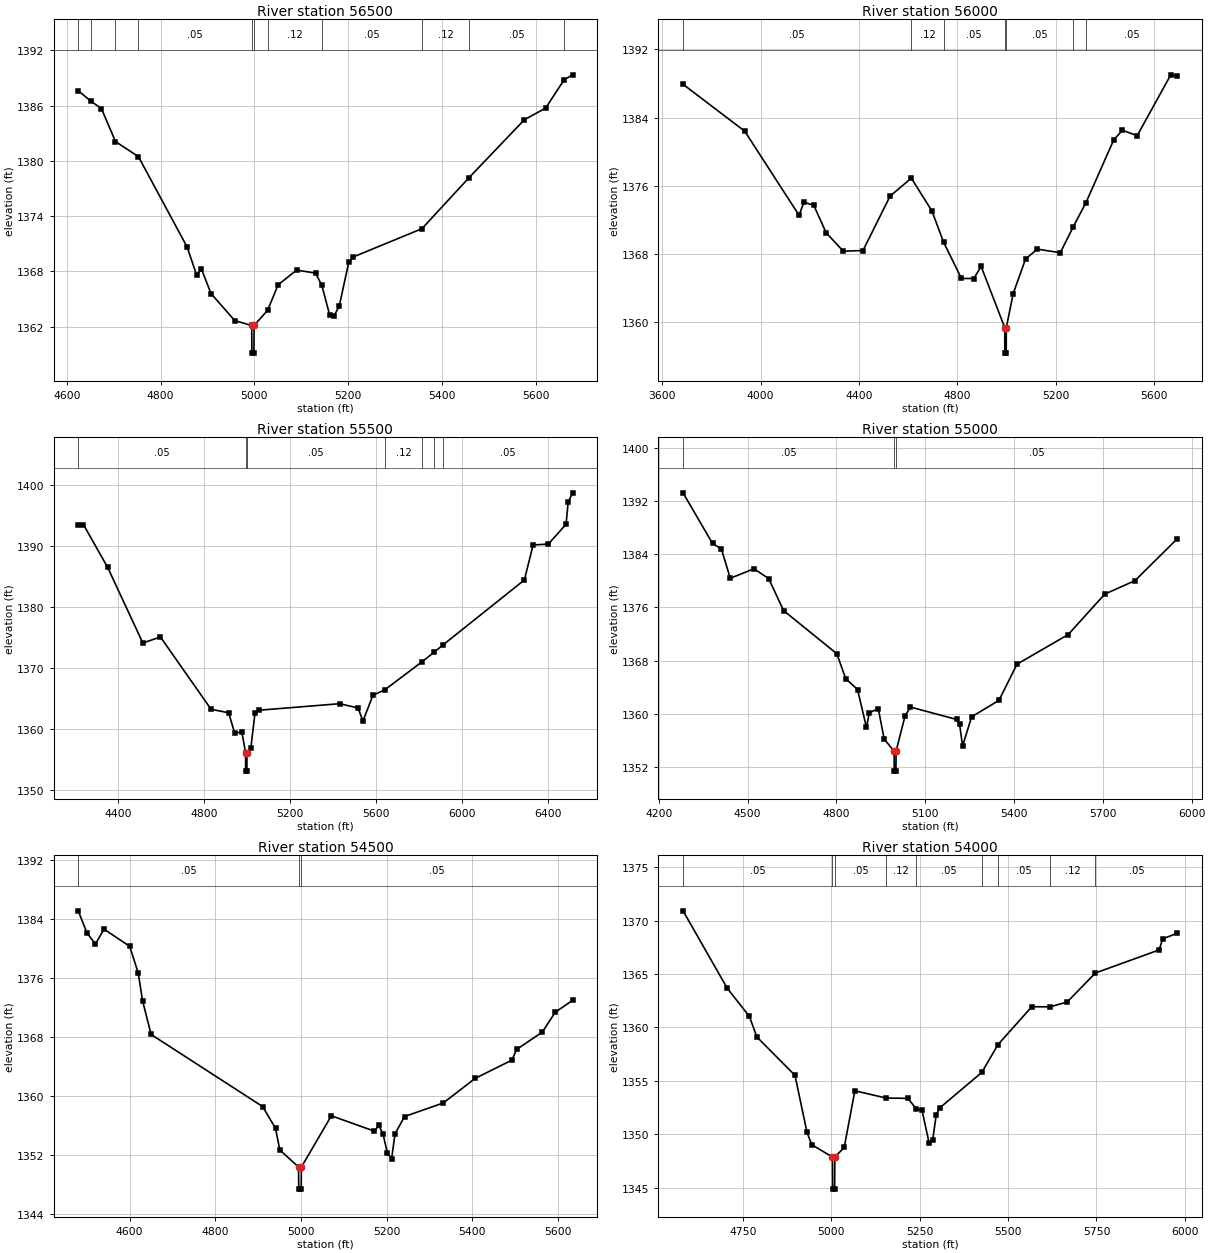
Type RM Length L Ch R = 1,56500,500,500,500
BEGIN DESCRIPTION:
BULLHEAD CREEK 113.0
END DESCRIPTION:
XS GIS Cut Line= 3
      2769506.93     10178421.74      2769876.74     10178355.44
      2770547.36     10178249.11
#Sta/Elev= 30
  4624.3 1387.62  4651.6 1386.46  4673.8 1385.68  4703.7 1382.10  4752.7 1380.46
  4856.7 1370.64  4877.0 1367.58  4887.2 1368.26  4907.5 1365.60  4958.3 1362.66
  4994.4 1362.13  4994.8 1359.13  4999.1 1359.13  4999.5 1362.13  5028.2 1363.77
  5050.7 1366.54  5090.1 1368.14  5130.6 1367.82  5144.0 1366.49  5160.9 1363.24
  5170.3 1363.20  5181.2 1364.23  5201.4 1368.98  5211.6 1369.58  5357.7 1372.64
  5458.4 1378.19  5576.1 1384.46  5621.6 1385.73  5660.9 1388.79  5679.0 1389.34
#Mann=11,-1,0
  4624.3    0.12       0  4651.6    0.05       0  4703.7    0.12       0
  4752.7    0.05       0  4994.4    0.05       0  4999.5    0.05       0
  5028.2    0.12       0  5144.0    0.05       0  5357.7    0.12       0
  5458.4    0.05       0  5660.9    0.12       0
Bank Sta=4994.4,4999.5
Exp/Cntr=0.3,0.1

Type RM Length L Ch R = 1,56000,500,500,500
BEGIN DESCRIPTION:
BULLHEAD CREEK 112.0
END DESCRIPTION:
XS GIS Cut Line= 3
      2768574.31     10178866.17      2769888.95     10178824.65
      2770577.40     10178734.71
#Sta/Elev= 30
  3684.7 1387.91  3935.6 1382.40  4156.3 1372.53  4176.3 1374.06  4216.3 1373.70
  4266.4 1370.48  4336.4 1368.31  4416.4 1368.39  4526.5 1374.78  4612.9 1376.89
  4696.6 1373.03  4744.2 1369.36  4816.6 1365.11  4866.7 1365.10  4896.7 1366.52
  4992.6 1359.34  4993.1 1356.34  4998.6 1356.34  4999.1 1359.34  5027.0 1363.33
  5077.4 1367.40  5125.2 1368.55  5218.6 1368.13  5269.9 1371.10  5322.8 1374.01
  5435.9 1381.39  5470.7 1382.50  5531.2 1381.88  5667.7 1389.02  5694.3 1388.88
#Mann=7,-1,0
  3684.7    0.05       0  4612.9    0.12       0  4744.2    0.05       0
  4992.6    0.05       0  4999.1    0.05       0  5269.9    0.12       0
  5322.8    0.05       0
Bank Sta=4992.6,4999.1
Exp/Cntr=0.3,0.1

Type RM Length L Ch R = 1,55500,500,500,500
BEGIN DESCRIPTION:
BULLHEAD CREEK 111.0
END DESCRIPTION:
XS GIS Cut Line= 3
      2768912.26     10179435.81      2769680.59     10179265.87
      2771165.76     10179554.73
#Sta/Elev= 30
  4213.1 1393.38  4237.1 1393.54  4349.7 1386.52  4513.6 1374.10  4595.5 1375.09
  4831.1 1363.23  4913.0 1362.65  4941.0 1359.31  4974.5 1359.50  4991.6 1356.08
  4992.1 1353.08  4997.7 1353.08  4998.2 1356.08  5016.1 1356.84  5035.7 1362.69
  5056.1 1363.08  5429.4 1364.14  5514.6 1363.45  5537.8 1361.30  5584.3 1365.53
  5639.9 1366.43  5811.9 1371.00  5867.5 1372.55  5911.6 1373.82  6288.8 1384.44
  6329.5 1390.18  6400.9 1390.34  6482.9 1393.60  6492.5 1397.17  6513.0 1398.74
#Mann=7,-1,0
  4213.1    0.05       0  4991.6    0.05       0  4998.2    0.05       0
  5639.9    0.12       0  5811.9    0.05       0  5867.5    0.12       0
  5911.6    0.05       0
Bank Sta=4991.6,4998.2
Exp/Cntr=0.3,0.1

Type RM Length L Ch R = 1,55000,500,500,500
BEGIN DESCRIPTION:
BULLHEAD CREEK 110.0
END DESCRIPTION:
XS GIS Cut Line= 3
      2768956.08     10179748.78      2769674.43     10179757.27
      2770605.66     10179953.11
#Sta/Elev= 30
  4281.6 1393.22  4381.2 1385.61  4411.2 1384.78  4441.2 1380.37  4521.2 1381.80
  4571.2 1380.32  4621.2 1375.52  4801.2 1369.03  4831.2 1365.29  4871.2 1363.65
  4901.2 1357.96  4911.2 1360.14  4941.2 1360.79  4961.2 1356.20  4994.8 1354.38
  4995.3 1351.38  5000.9 1351.38  5001.4 1354.38  5031.9 1359.71  5050.0 1361.01
  5205.7 1359.15  5215.9 1358.44  5226.1 1355.17  5256.7 1359.55  5349.0 1362.02
  5410.0 1367.46  5582.9 1371.91  5706.4 1377.99  5808.6 1380.02  5951.6 1386.32
#Mann=3,-1,0
  4281.6    0.05       0  4994.8    0.05       0  5001.4    0.05       0
Bank Sta=4994.8,5001.4
Exp/Cntr=0.3,0.1

Type RM Length L Ch R = 1,54500,500,500,500
BEGIN DESCRIPTION:
BULLHEAD CREEK 109.0
END DESCRIPTION:
XS GIS Cut Line= 3
      2769055.73     10180203.11      2769574.93     10180233.79
      2770205.73     10180303.12
#Sta/Elev= 30
  4479.9 1385.17  4499.9 1382.21  4519.9 1380.65  4540.0 1382.69  4600.1 1380.35
  4620.1 1376.71  4630.1 1372.98  4650.1 1368.40  4910.6 1358.62  4940.7 1355.68
  4950.7 1352.73  4994.5 1350.42  4995.0 1347.42  5000.7 1347.42  5001.2 1350.42
  5071.2 1357.37  5171.8 1355.28  5181.8 1356.08  5191.9 1354.91  5202.0 1352.31
  5212.0 1351.57  5219.9 1354.93  5242.2 1357.27  5332.7 1359.11  5407.0 1362.44
  5493.0 1364.92  5503.8 1366.36  5564.1 1368.73  5594.3 1371.42  5634.6 1373.02
#Mann=3,-1,0
  4479.9    0.05       0  4994.5    0.05       0  5001.2    0.05       0
Bank Sta=4994.5,5001.2
Exp/Cntr=0.3,0.1

Type RM Length L Ch R = 1,54000,500,500,500
BEGIN DESCRIPTION:
BULLHEAD CREEK 108.0
END DESCRIPTION:
XS GIS Cut Line= 3
      2769105.02     10180583.24      2769509.49     10180696.02
      2770487.00     10180645.74
#Sta/Elev= 30
  4580.1 1370.91  4705.0 1363.67  4767.7 1361.03  4789.0 1359.10  4896.8 1355.51
  4930.9 1350.17  4944.1 1349.02  5002.9 1347.85  5003.4 1344.85  5009.1 1344.85
  5009.6 1347.85  5036.2 1348.75  5066.3 1354.06  5154.8 1353.38  5216.5 1353.35
  5240.7 1352.34  5256.5 1352.22  5276.6 1349.14  5286.6 1349.47  5296.6 1351.80
  5306.6 1352.46  5425.6 1355.78  5471.3 1358.38  5566.9 1361.93  5618.6 1361.92
  5667.1 1362.37  5747.1 1365.09  5927.4 1367.25  5937.5 1368.29  5978.8 1368.81
#Mann=9,-1,0
  4580.1    0.05       0  5002.9    0.05       0  5009.6    0.05       0
  5154.8    0.12       0  5240.7    0.05       0  5425.6    0.12       0
  5471.3    0.05       0  5618.6    0.12       0  5747.1    0.05       0
Bank Sta=5002.9,5009.6
Exp/Cntr=0.3,0.1

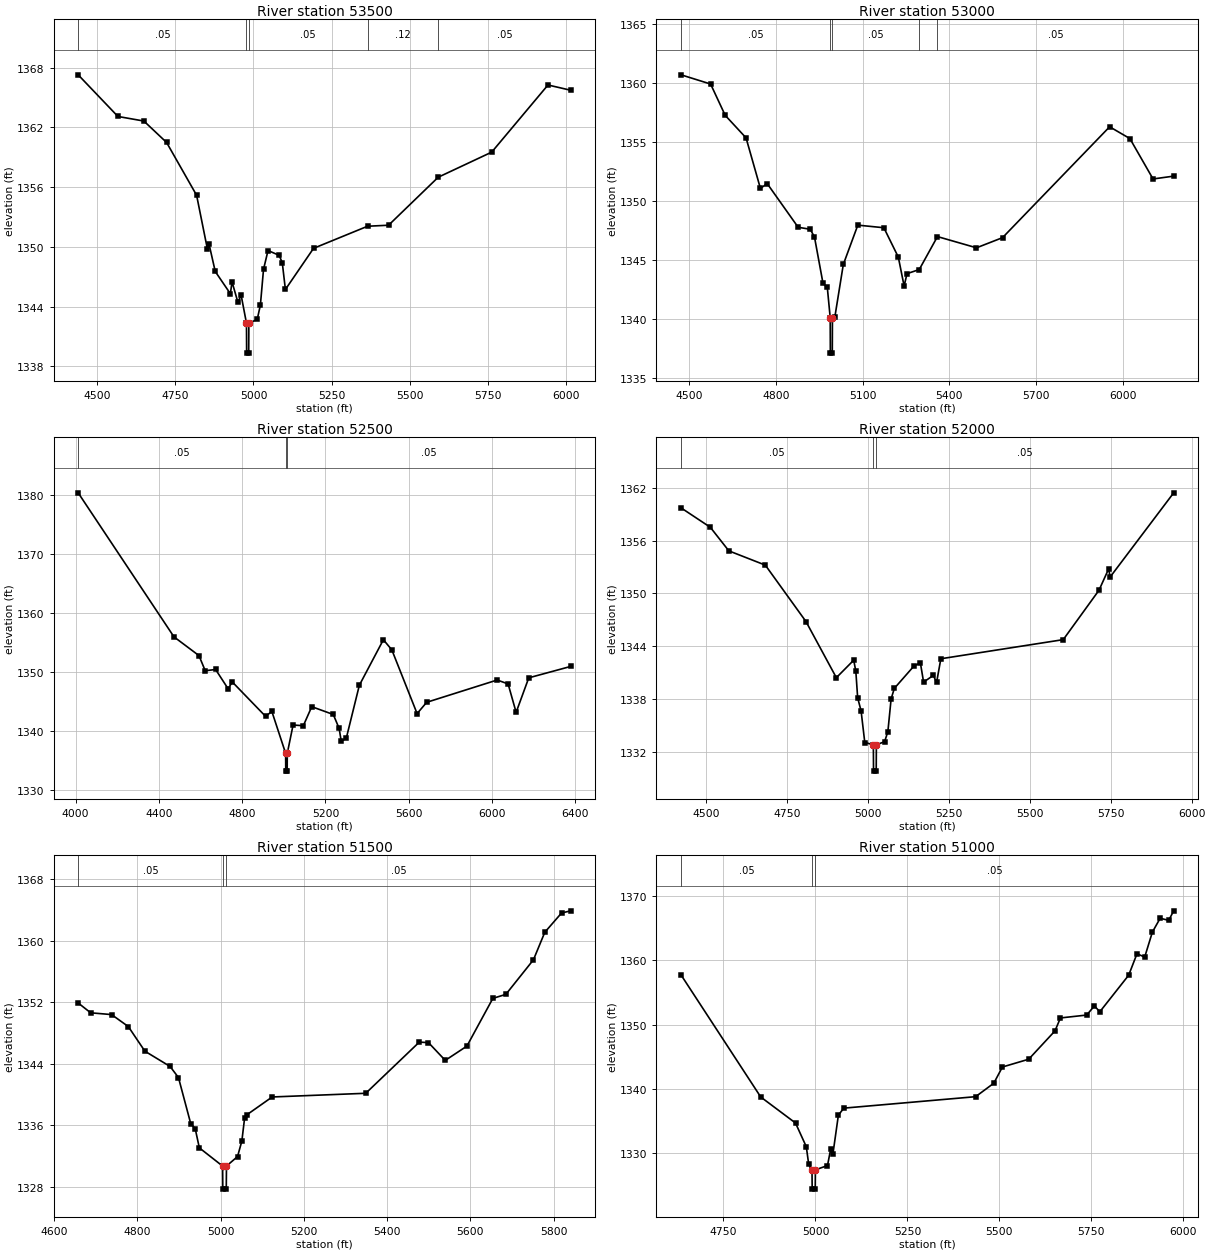
Type RM Length L Ch R = 1,53500,500,500,500
BEGIN DESCRIPTION:
BULLHEAD CREEK 107.0
END DESCRIPTION:
XS GIS Cut Line= 3
      2768973.07     10181027.69      2769513.64     10181177.34
      2770528.59     10181194.35
#Sta/Elev= 30
  4439.1 1367.27  4566.3 1363.09  4649.3 1362.63  4722.0 1360.48  4818.0 1355.18
  4852.3 1349.82  4857.5 1350.32  4877.6 1347.53  4926.1 1345.29  4931.3 1346.49
  4950.2 1344.43  4960.4 1345.16  4977.6 1342.33  4978.1 1339.33  4984.7 1339.33
  4985.2 1342.33  5012.0 1342.72  5022.1 1344.16  5032.1 1347.74  5046.5 1349.63
  5082.1 1349.15  5092.1 1348.41  5102.1 1345.72  5192.1 1349.85  5365.0 1352.07
  5432.1 1352.17  5591.0 1356.99  5762.2 1359.51  5942.2 1366.25  6015.1 1365.72
#Mann=5,-1,0
  4439.1    0.05       0  4977.6    0.05       0  4985.2    0.05       0
  5365.0    0.12       0  5591.0    0.05       0
Bank Sta=4977.6,4985.2
Exp/Cntr=0.3,0.1

Type RM Length L Ch R = 1,53000,500,500,500
BEGIN DESCRIPTION:
BULLHEAD CREEK 106.0
END DESCRIPTION:
XS GIS Cut Line= 3
      2768882.77     10181312.40      2769312.16     10181618.12
      2770486.93     10181645.74
#Sta/Elev= 30
  4472.9 1360.71  4574.9 1359.93  4625.3 1357.28  4697.4 1355.37  4747.0 1351.09
  4770.4 1351.50  4877.4 1347.80  4919.2 1347.63  4933.9 1346.97  4963.4 1343.04
  4978.2 1342.70  4988.2 1340.14  4988.7 1337.14  4995.4 1337.14  4995.9 1340.14
  5004.3 1340.21  5033.5 1344.65  5083.6 1347.98  5173.6 1347.76  5223.6 1345.27
  5243.6 1342.82  5253.6 1343.87  5295.9 1344.22  5358.8 1347.01  5493.7 1346.06
  5583.7 1346.92  5953.8 1356.31  6023.8 1355.31  6103.8 1351.89  6175.1 1352.13
#Mann=5,-1,0
  4472.9    0.05       0  4988.2    0.03       0  4995.9    0.05       0
  5295.9    0.12       0  5358.8    0.05       0
Bank Sta=4988.2,4995.9
Exp/Cntr=0.3,0.1

Type RM Length L Ch R = 1,52500,500,500,500
BEGIN DESCRIPTION:
BULLHEAD CREEK 105.0
END DESCRIPTION:
XS GIS Cut Line= 3
      2768255.64     10182103.11      2769243.13     10182074.45
      2770605.00     10181861.02
#Sta/Elev= 30
  4012.1 1380.32  4472.3 1355.96  4592.4 1352.79  4622.4 1350.23  4672.4 1350.44
  4732.4 1347.18  4752.5 1348.33  4912.5 1342.51  4942.5 1343.35  5008.8 1336.25
  5009.3 1333.25  5016.1 1333.25  5016.6 1336.25  5044.5 1341.05  5093.7 1340.93
  5134.2 1344.15  5237.6 1342.83  5265.8 1340.47  5275.9 1338.28  5300.2 1338.83
  5362.9 1347.78  5478.3 1355.47  5518.8 1353.77  5640.3 1342.98  5686.3 1344.89
  6024.9 1348.66  6077.5 1348.00  6116.0 1343.19  6176.7 1349.03  6378.5 1350.96
#Mann=3,-1,0
  4012.1    0.05       0  5008.8    0.05       0  5016.6    0.05       0
Bank Sta=5008.8,5016.6
Exp/Cntr=0.3,0.1

Type RM Length L Ch R = 1,52000,500,500,500
BEGIN DESCRIPTION:
BULLHEAD CREEK 104.0
END DESCRIPTION:
XS GIS Cut Line= 3
      2769105.66     10182653.13      2769613.90     10182381.03
      2770555.65     10182453.11
#Sta/Elev= 30
  4423.5 1359.71  4513.7 1357.51  4571.0 1354.83  4683.6 1353.21  4809.2 1346.80
  4902.9 1340.43  4956.6 1342.42  4963.1 1341.14  4968.7 1338.15  4979.3 1336.66
  4990.7 1333.07  5017.2 1332.82  5017.7 1329.82  5026.0 1329.82  5026.5 1332.82
  5051.9 1333.16  5062.0 1334.31  5072.0 1338.02  5082.0 1339.22  5142.2 1341.74
  5162.3 1342.13  5172.3 1339.93  5202.4 1340.69  5212.4 1339.89  5225.6 1342.58
  5603.5 1344.75  5713.9 1350.36  5743.5 1352.77  5748.5 1351.87  5944.5 1361.42
#Mann=3,-1,0
  4423.5    0.05       0  5017.2    0.03       0  5026.5    0.05       0
Bank Sta=5017.2,5026.5
Exp/Cntr=0.3,0.1

Type RM Length L Ch R = 1,51500,500,500,500
BEGIN DESCRIPTION:
BULLHEAD CREEK 103.0
END DESCRIPTION:
XS GIS Cut Line= 3
      2769455.68     10182803.11      2769796.66     10182834.26
      2770605.69     10182603.11
#Sta/Elev= 30
  4657.6 1351.90  4687.7 1350.62  4737.9 1350.39  4778.1 1348.83  4817.9 1345.63
  4878.5 1343.64  4898.6 1342.20  4928.1 1336.20  4938.8 1335.56  4948.8 1333.05
  5004.7 1330.68  5005.2 1327.68  5013.5 1327.68  5014.0 1330.68  5040.6 1331.92
  5051.0 1333.95  5057.5 1336.90  5062.7 1337.34  5123.8 1339.67  5348.7 1340.15
  5477.4 1346.81  5499.5 1346.74  5539.8 1344.43  5591.8 1346.29  5654.2 1352.50
  5685.4 1353.02  5751.7 1357.52  5779.0 1361.10  5819.3 1363.61  5841.4 1363.89
#Mann=3,-1,0
  4657.6    0.05       0  5004.7    0.03       0  5014.0    0.05       0
Bank Sta=5004.7,5014
Exp/Cntr=0.3,0.1

Type RM Length L Ch R = 1,51000,500,500,500
BEGIN DESCRIPTION:
BULLHEAD CREEK 102.0
END DESCRIPTION:
XS GIS Cut Line= 3
      2769655.68     10183353.11      2770009.85     10183264.02
      2770805.65     10182703.13
#Sta/Elev= 30
  4634.8 1357.69  4851.3 1338.74  4945.8 1334.70  4975.1 1331.02  4981.7 1328.27
  4990.6 1327.43  4991.1 1324.43  4999.4 1324.43  4999.9 1327.43  5032.7 1328.09
  5041.4 1330.65  5047.5 1329.91  5062.3 1335.92  5077.1 1337.01  5435.3 1338.79
  5484.7 1340.88  5508.1 1343.40  5579.6 1344.61  5651.0 1349.01  5665.8 1351.02
  5737.2 1351.47  5758.1 1352.89  5772.9 1351.98  5851.3 1357.66  5873.9 1361.00
  5894.8 1360.47  5915.7 1364.36  5936.9 1366.51  5960.1 1366.18  5973.6 1367.66
#Mann=3,-1,0
  4634.8    0.05       0  4990.6    0.05       0  4999.9    0.05       0
Bank Sta=4990.6,4999.9
Exp/Cntr=0.3,0.1