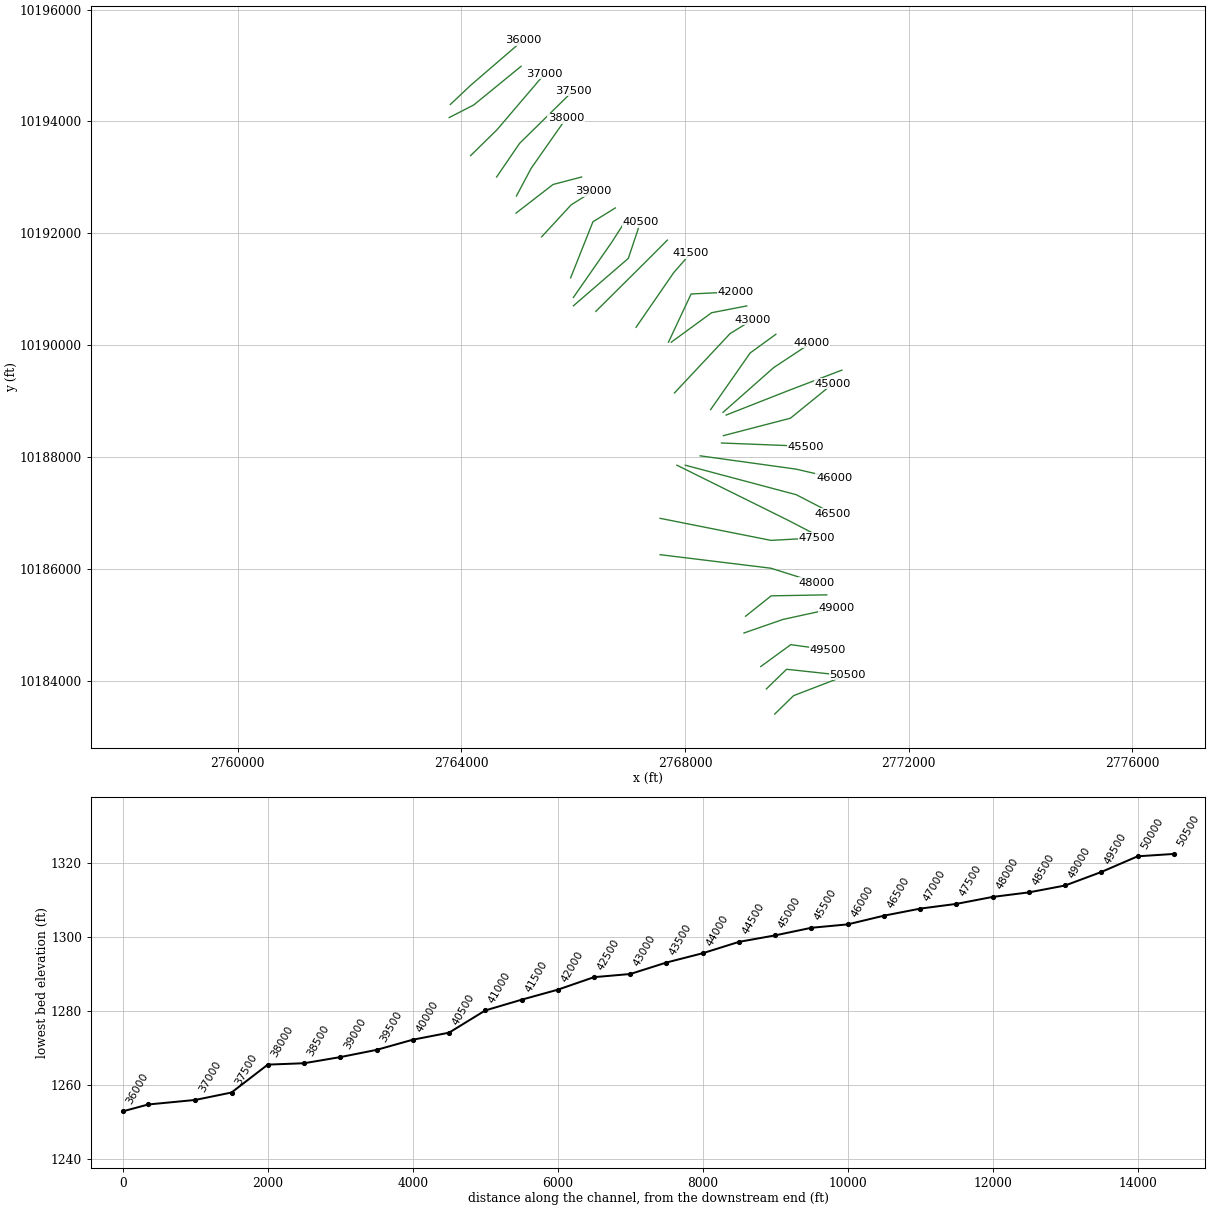
HEC-RAS study BULLHEAD CREEK.prj: BULLHEAD CREEK Base Level Engineering

--- BULLHEAD CREEK.g01 (geometry) --- (continued)

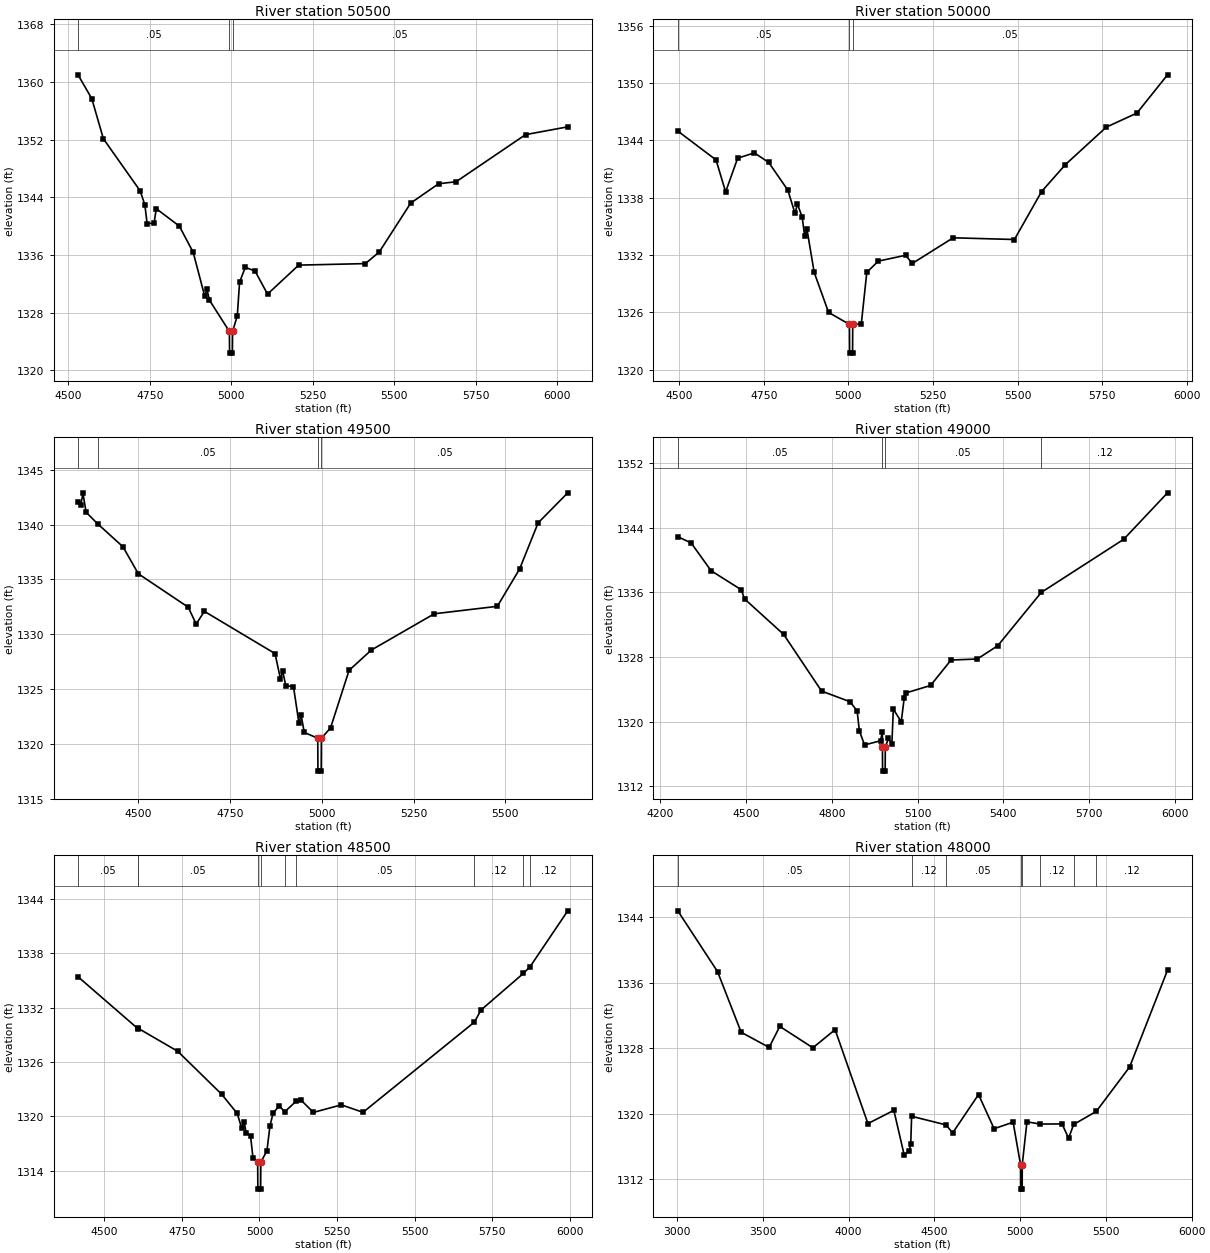
Type RM Length L Ch R = 1,50500,500,500,500
BEGIN DESCRIPTION:
BULLHEAD CREEK 101.0
END DESCRIPTION:
XS GIS Cut Line= 3
      2769605.71     10183403.14      2769941.61     10183732.02
      2770905.66     10184103.10
#Sta/Elev= 30
  4529.9 1360.97  4572.2 1357.66  4607.7 1352.11  4720.8 1344.87  4735.0 1342.94
  4742.0 1340.35  4763.2 1340.41  4770.2 1342.41  4841.0 1339.99  4883.4 1336.36
  4918.8 1330.26  4925.8 1331.24  4933.0 1329.75  4994.5 1325.39  4995.0 1322.39
  5003.7 1322.39  5004.2 1325.39  5018.7 1327.56  5025.8 1332.25  5043.3 1334.28
  5073.3 1333.77  5111.5 1330.57  5207.2 1334.59  5411.8 1334.80  5454.4 1336.41
  5551.0 1343.19  5636.6 1345.87  5690.3 1346.15  5903.4 1352.68  6033.0 1353.76
#Mann=3,-1,0
  4529.9    0.05       0  4994.5    0.03       0  5004.2    0.05       0
Bank Sta=4994.5,5004.2
Exp/Cntr=0.3,0.1

Type RM Length L Ch R = 1,50000,500,500,500
BEGIN DESCRIPTION:
BULLHEAD CREEK 100.0
END DESCRIPTION:
XS GIS Cut Line= 3
      2769455.66     10183853.09      2769817.65     10184204.06
      2770755.64     10184103.12
#Sta/Elev= 30
  4495.8 1344.97  4608.9 1341.95  4637.2 1338.61  4672.7 1342.13  4722.1 1342.69
  4764.5 1341.69  4821.1 1338.79  4842.4 1336.35  4849.4 1337.35  4863.5 1335.97
  4870.7 1334.02  4877.7 1334.68  4899.0 1330.19  4941.5 1326.01  5003.2 1324.75
  5003.7 1321.75  5012.4 1321.75  5012.9 1324.75  5038.2 1324.80  5054.5 1330.20
  5088.5 1331.37  5169.0 1331.98  5189.1 1331.13  5309.8 1333.81  5490.8 1333.63
  5571.3 1338.65  5641.7 1341.47  5762.4 1345.38  5852.9 1346.85  5943.4 1350.85
#Mann=3,-1,0
  4495.8    0.05       0  5003.2    0.05       0  5012.9    0.05       0
Bank Sta=5003.2,5012.9
Exp/Cntr=0.3,0.1

Type RM Length L Ch R = 1,49500,500,500,500
BEGIN DESCRIPTION:
BULLHEAD CREEK 99.0
END DESCRIPTION:
XS GIS Cut Line= 3
      2769355.71     10184253.13      2769892.09     10184644.17
      2770555.68     10184553.11
#Sta/Elev= 30
  4336.2 1342.08  4343.5 1341.78  4349.7 1342.84  4358.2 1341.13  4389.4 1340.08
  4458.6 1337.98  4500.3 1335.52  4636.3 1332.47  4657.9 1330.93  4680.3 1332.09
  4872.7 1328.24  4887.4 1325.94  4893.6 1326.61  4902.0 1325.31  4922.9 1325.23
  4937.6 1321.93  4943.8 1322.60  4952.3 1321.05  4989.0 1320.52  4989.5 1317.52
  4998.4 1317.52  4998.9 1320.52  5023.8 1321.46  5074.3 1326.71  5134.8 1328.56
  5306.4 1331.87  5478.0 1332.55  5538.6 1335.95  5589.1 1340.16  5669.8 1342.90
#Mann=4,-1,0
  4336.2    0.12       0  4389.4    0.05       0  4989.0    0.03       0
  4998.9    0.05       0
Bank Sta=4989,4998.9
Exp/Cntr=0.3,0.1

Type RM Length L Ch R = 1,49000,500,500,500
BEGIN DESCRIPTION:
BULLHEAD CREEK 98.0
END DESCRIPTION:
XS GIS Cut Line= 3
      2769055.73     10184853.13      2769753.50     10185095.28
      2770705.69     10185303.11
#Sta/Elev= 30
  4261.4 1342.88  4308.0 1342.11  4377.8 1338.67  4483.6 1336.31  4494.8 1335.18
  4631.8 1330.78  4764.4 1323.77  4864.7 1322.44  4888.9 1321.28  4896.5 1318.87
  4914.7 1317.10  4970.6 1317.62  4977.0 1318.72  4977.3 1316.86  4977.8 1313.86
  4986.8 1313.86  4987.3 1316.86  4998.5 1317.90  5010.3 1317.26  5015.4 1321.52
  5043.2 1319.98  5053.4 1322.91  5059.4 1323.54  5145.5 1324.46  5217.2 1327.61
  5309.3 1327.74  5380.9 1329.39  5532.9 1335.98  5821.1 1342.55  5974.6 1348.31
#Mann=4,-1,0
  4261.4    0.05       0  4977.3    0.03       0  4987.3    0.05       0
  5532.9    0.12       0
Bank Sta=4977.3,4987.3
Exp/Cntr=0.3,0.1

Type RM Length L Ch R = 1,48500,500,500,500
BEGIN DESCRIPTION:
BULLHEAD CREEK 97.0
END DESCRIPTION:
XS GIS Cut Line= 3
      2769084.21     10185152.71      2769541.70     10185517.13
      2770535.55     10185534.63
#Sta/Elev= 30
  4415.1 1335.39  4607.4 1329.69  4609.0 1329.71  4736.6 1327.18  4878.4 1322.44
  4928.4 1320.33  4942.5 1318.73  4950.5 1319.43  4956.9 1318.23  4971.3 1317.85
  4979.3 1315.41  4994.3 1315.00  4994.8 1312.00  5003.9 1312.00  5004.4 1315.00
  5024.0 1316.19  5034.0 1318.99  5044.0 1320.37  5064.0 1321.18  5081.2 1320.51
  5118.3 1321.68  5134.0 1321.80  5174.0 1320.45  5264.0 1321.28  5334.0 1320.46
  5693.2 1330.40  5714.1 1331.72  5851.0 1335.76  5872.8 1336.51  5994.0 1342.65
#Mann=10,-1,0
  4415.1    0.05       0  4607.4    0.12       0  4609.0    0.05       0
  4994.3    0.05       0  5004.4    0.05       0  5081.2    0.12       0
  5118.3    0.05       0  5693.2    0.12       0  5851.0    0.05       0
  5872.8    0.12       0
Bank Sta=4994.3,5004.4
Exp/Cntr=0.3,0.1

Type RM Length L Ch R = 1,48000,500,500,500
BEGIN DESCRIPTION:
BULLHEAD CREEK 96.0
END DESCRIPTION:
XS GIS Cut Line= 3
      2767555.69     10186253.11      2769536.06     10186011.17
      2770355.70     10185753.11
#Sta/Elev= 30
  3004.9 1344.78  3236.6 1337.35  3374.3 1329.94  3537.3 1328.09  3599.3 1330.66
  3792.0 1328.04  3921.7 1330.26  4113.1 1318.78  4264.2 1320.40  4324.6 1314.93
  4354.9 1315.45  4362.7 1316.32  4367.7 1319.67  4568.7 1318.62  4606.7 1317.63
  4757.8 1322.33  4848.5 1318.15  4959.3 1318.95  5002.5 1313.77  5003.0 1310.77
  5012.1 1310.77  5012.6 1313.77  5039.9 1319.00  5117.1 1318.72  5244.6 1318.74
  5282.7 1316.98  5312.1 1318.67  5444.2 1320.27  5638.4 1325.70  5859.3 1337.53
#Mann=8,-1,0
  3004.9    0.05       0  4367.7    0.12       0  4568.7    0.05       0
  5002.5    0.05       0  5012.6    0.05       0  5117.1    0.12       0
  5312.1    0.05       0  5444.2    0.12       0
Bank Sta=5002.5,5012.6
Exp/Cntr=0.3,0.1

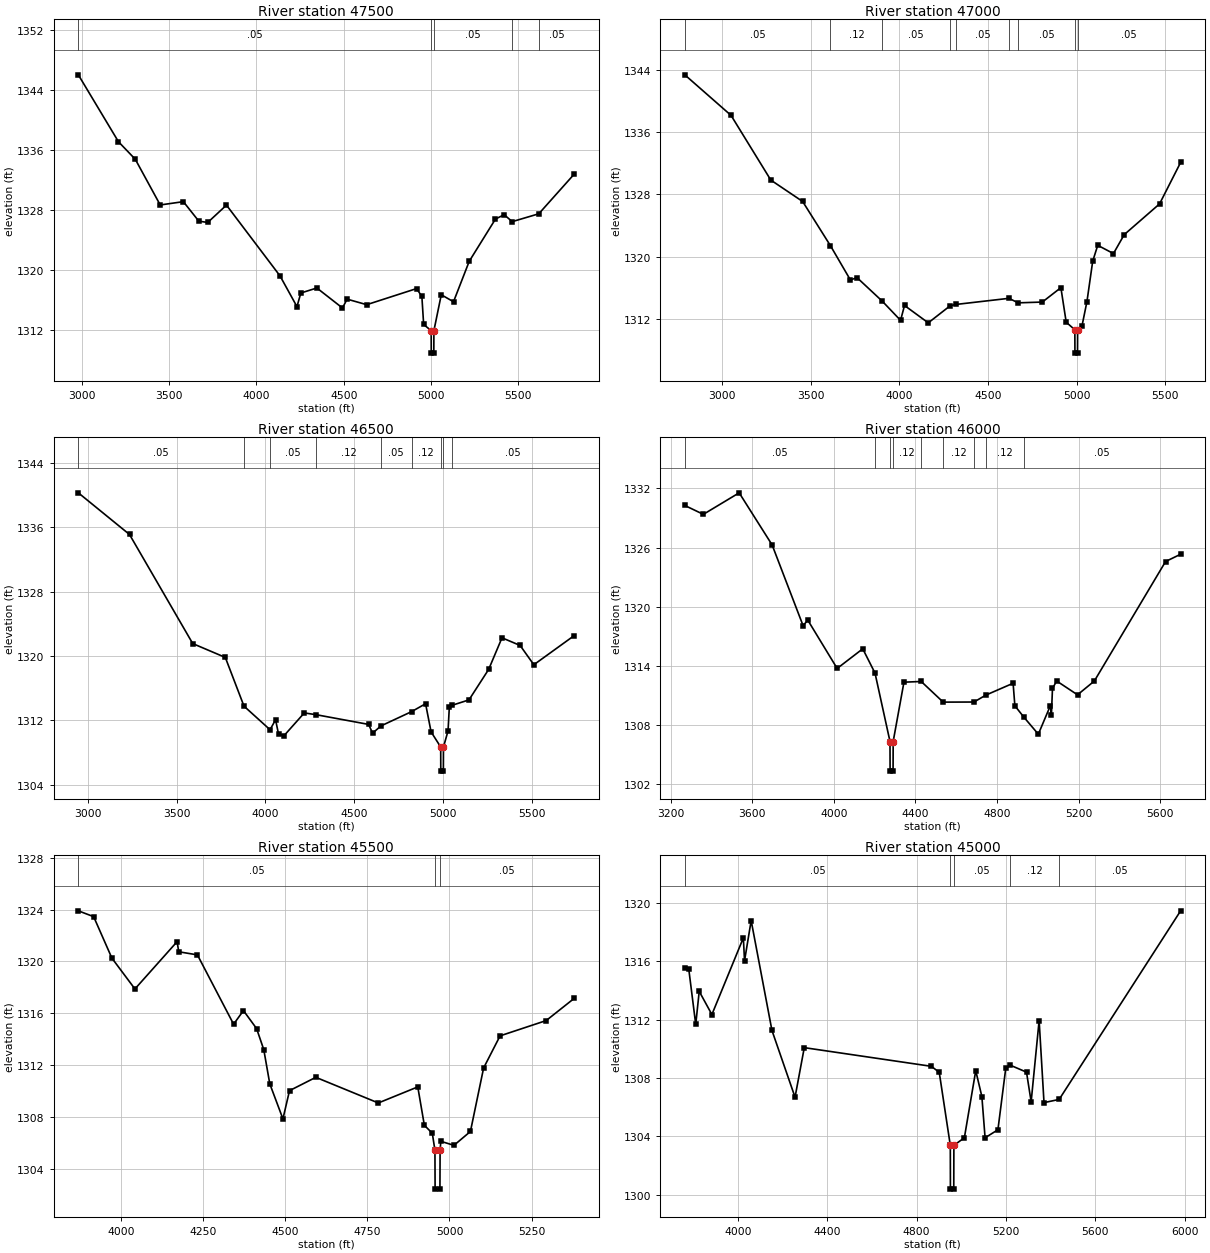
Type RM Length L Ch R = 1,47500,500,500,500
BEGIN DESCRIPTION:
BULLHEAD CREEK 95.0
END DESCRIPTION:
XS GIS Cut Line= 3
      2767555.67     10186903.12      2769537.03     10186508.88
      2770355.73     10186553.11
#Sta/Elev= 30
  2979.8 1346.06  3209.8 1337.12  3306.1 1334.78  3448.8 1328.68  3581.4 1329.12
  3669.8 1326.52  3720.9 1326.34  3828.3 1328.66  4134.9 1319.21  4232.1 1315.10
  4254.3 1316.92  4346.1 1317.59  4492.7 1314.92  4519.4 1316.10  4631.6 1315.36
  4917.1 1317.51  4947.6 1316.46  4957.8 1312.72  5000.9 1311.89  5001.4 1308.89
  5016.0 1308.89  5016.5 1311.89  5058.7 1316.69  5128.8 1315.75  5219.0 1321.16
  5369.2 1326.80  5419.3 1327.38  5464.9 1326.45  5617.3 1327.50  5819.9 1332.79
#Mann=5,-1,0
  2979.8    0.05       0  5000.9    0.05       0  5016.5    0.05       0
  5464.9    0.12       0  5617.3    0.05       0
Bank Sta=5000.9,5016.5
Exp/Cntr=0.3,0.1

Type RM Length L Ch R = 1,47000,500,500,500
BEGIN DESCRIPTION:
BULLHEAD CREEK 94.0
END DESCRIPTION:
XS GIS Cut Line= 3
      2767855.71     10187853.10      2769835.58     10186872.74
      2770355.65     10186603.13
#Sta/Elev= 30
  2790.7 1343.36  3051.4 1338.15  3275.6 1329.84  3455.0 1327.09  3612.0 1321.40
  3724.2 1317.01  3761.5 1317.31  3904.9 1314.26  4007.0 1311.82  4029.3 1313.73
  4163.2 1311.50  4286.4 1313.69  4317.8 1313.86  4618.2 1314.65  4669.8 1314.07
  4806.2 1314.17  4910.8 1316.02  4940.8 1311.58  4989.5 1310.61  4990.0 1307.61
  5004.6 1307.61  5005.1 1310.61  5030.0 1311.13  5057.8 1314.24  5090.2 1319.42
  5118.5 1321.46  5207.1 1320.40  5267.8 1322.83  5467.0 1326.78  5585.8 1332.11
#Mann=9,-1,0
  2790.7    0.05       0  3612.0    0.12       0  3904.9    0.05       0
  4286.4    0.12       0  4317.8    0.05       0  4618.2    0.12       0
  4669.8    0.05       0  4989.5    0.03       0  5005.1    0.05       0
Bank Sta=4989.5,5005.1
Exp/Cntr=0.3,0.1

Type RM Length L Ch R = 1,46500,500,500,500
BEGIN DESCRIPTION:
BULLHEAD CREEK 93.0
END DESCRIPTION:
XS GIS Cut Line= 3
      2768005.69     10187853.11      2769990.31     10187325.35
      2770646.69     10186986.01
#Sta/Elev= 30
  2946.4 1340.31  3234.6 1335.13  3590.8 1321.56  3774.2 1319.84  3879.4 1313.78
  4026.1 1310.85  4057.1 1312.08  4074.3 1310.28  4105.3 1310.12  4219.1 1312.94
  4287.5 1312.71  4581.3 1311.51  4603.7 1310.42  4650.5 1311.32  4823.4 1313.10
  4902.1 1314.08  4933.1 1310.58  4987.2 1308.70  4987.7 1305.70  5002.3 1305.70
  5002.8 1308.70  5028.6 1310.70  5035.9 1313.68  5051.8 1313.89  5146.6 1314.56
  5257.3 1318.35  5332.5 1322.28  5434.5 1321.33  5511.8 1318.93  5738.9 1322.55
#Mann=9,-1,0
  2946.4    0.05       0  3879.4    0.12       0  4026.1    0.05       0
  4287.5    0.12       0  4650.5    0.05       0  4823.4    0.12       0
  4987.2    0.07       0  5002.8    0.12       0  5051.8    0.05       0
Bank Sta=4987.2,5002.8
Exp/Cntr=0.3,0.1

Type RM Length L Ch R = 1,46000,500,500,500
BEGIN DESCRIPTION:
BULLHEAD CREEK 92.0
END DESCRIPTION:
XS GIS Cut Line= 3
      2768271.66     10188020.74      2769985.48     10187783.19
      2770667.55     10187624.90
#Sta/Elev= 30
  3269.8 1330.26  3360.7 1329.36  3536.3 1331.54  3697.9 1326.26  3849.3 1318.10
  3873.1 1318.63  4016.6 1313.75  4142.1 1315.74  4202.2 1313.28  4275.6 1306.35
  4276.1 1303.35  4290.7 1303.35  4291.2 1306.35  4344.0 1312.36  4428.7 1312.43
  4536.3 1310.34  4687.2 1310.35  4745.4 1311.05  4879.1 1312.25  4887.7 1309.97
  4930.1 1308.86  5002.7 1307.09  5061.7 1309.98  5066.8 1309.04  5072.1 1311.72
  5092.6 1312.48  5194.8 1311.08  5277.4 1312.48  5626.4 1324.58  5700.2 1325.32
#Mann=9,-1,0
  3269.8    0.05       0  4202.2    0.12       0  4275.6    0.05       0
  4291.2    0.12       0  4428.7    0.05       0  4536.3    0.12       0
  4687.2    0.05       0  4745.4    0.12       0  4930.1    0.05       0
Bank Sta=4275.6,4291.2
Exp/Cntr=0.3,0.1

Type RM Length L Ch R = 1,45500,500,500,500
BEGIN DESCRIPTION:
BULLHEAD CREEK 91.0
END DESCRIPTION:
XS GIS Cut Line= 3
      2768653.66     10188249.91      2769782.01     10188206.05
      2770160.55     10188180.46
#Sta/Elev= 30
  3870.8 1323.91  3917.4 1323.46  3972.9 1320.26  4043.0 1317.88  4171.3 1321.53
  4176.3 1320.75  4233.1 1320.51  4343.2 1315.16  4373.2 1316.21  4413.2 1314.82
  4435.1 1313.19  4453.3 1310.56  4493.3 1307.85  4513.3 1310.03  4593.4 1311.06
  4783.5 1309.08  4903.6 1310.32  4923.6 1307.36  4947.8 1306.74  4955.8 1305.43
  4956.3 1302.43  4971.0 1302.43  4971.5 1305.43  4973.7 1306.12  5013.7 1305.81
  5063.8 1306.88  5103.9 1311.78  5154.0 1314.26  5294.3 1315.44  5379.4 1317.15
#Mann=3,-1,0
  3870.8    0.05       0  4955.8    0.05       0  4971.5    0.05       0
Bank Sta=4955.8,4971.5
Exp/Cntr=0.3,0.1

Type RM Length L Ch R = 1,45000,500,500,500
BEGIN DESCRIPTION:
BULLHEAD CREEK 90.0
END DESCRIPTION:
XS GIS Cut Line= 3
      2768688.37     10188381.86      2769885.57     10188693.11
      2770646.65     10189312.38
#Sta/Elev= 30
  3763.0 1315.57  3780.9 1315.45  3811.9 1311.67  3827.5 1313.94  3884.2 1312.35
  4025.0 1317.61  4030.2 1316.03  4059.9 1318.79  4152.9 1311.26  4256.2 1306.68
  4297.5 1310.08  4865.9 1308.80  4901.3 1308.39  4950.8 1303.38  4951.3 1300.38
  4966.3 1300.38  4966.8 1303.38  5013.7 1303.90  5064.6 1308.50  5092.0 1306.73
  5106.4 1303.90  5163.8 1304.45  5199.0 1308.68  5220.1 1308.87  5291.7 1308.40
  5312.5 1306.37  5348.2 1311.94  5370.0 1306.31  5437.8 1306.53  5981.2 1319.46
#Mann=5,-1,0
  3763.0    0.05       0  4950.8    0.03       0  4966.8    0.05       0
  5220.1    0.12       0  5437.8    0.05       0
Bank Sta=4950.8,4966.8
Exp/Cntr=0.3,0.1

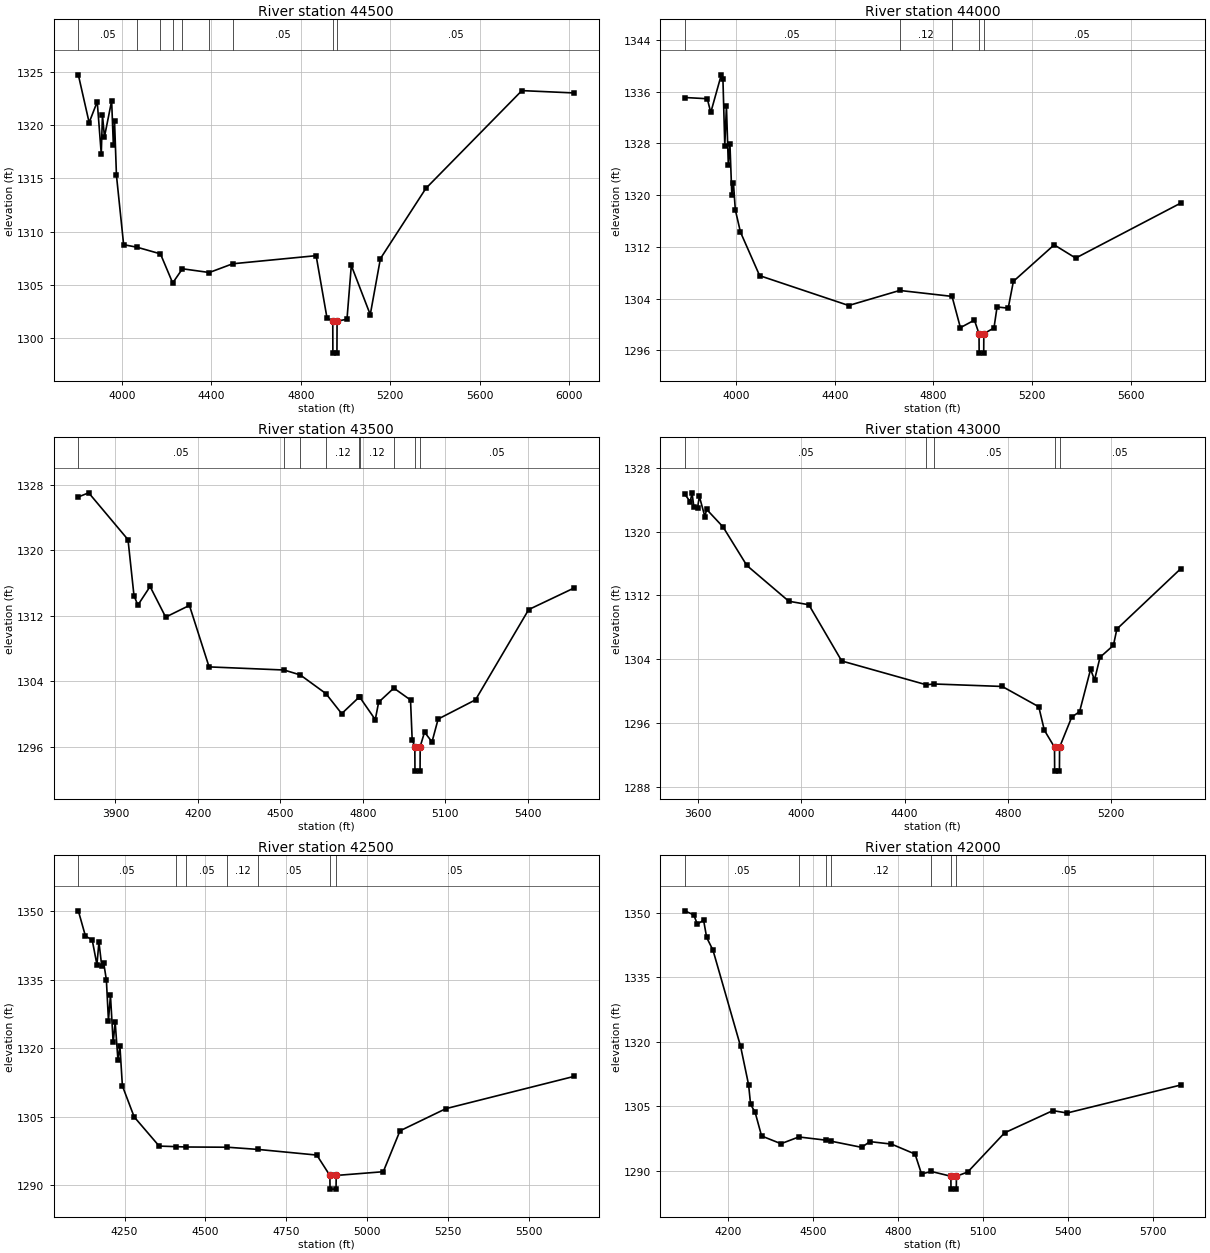
Type RM Length L Ch R = 1,44500,500,500,500
BEGIN DESCRIPTION:
BULLHEAD CREEK 89.0
END DESCRIPTION:
XS GIS Cut Line= 3
      2768736.93     10188749.89      2769849.66     10189187.53
      2770805.65     10189553.10
#Sta/Elev= 30
  3804.3 1324.72  3852.7 1320.24  3888.9 1322.20  3906.9 1317.30  3912.3 1320.95
  3921.2 1318.90  3953.4 1322.28  3961.1 1318.10  3966.4 1320.36  3974.9 1315.29
  4007.1 1308.79  4067.5 1308.55  4171.8 1307.93  4226.6 1305.20  4270.3 1306.53
  4390.5 1306.18  4495.1 1307.00  4868.6 1307.76  4917.4 1301.90  4943.1 1301.62
  4943.6 1298.62  4961.8 1298.62  4962.3 1301.62  5006.7 1301.80  5026.1 1306.84
  5110.9 1302.23  5156.3 1307.48  5359.8 1314.07  5789.5 1323.24  6023.5 1323.02
#Mann=9,-1,0
  3804.3    0.05       0  4067.5    0.12       0  4171.8    0.05       0
  4226.6    0.12       0  4270.3    0.05       0  4390.5    0.12       0
  4495.1    0.05       0  4943.1    0.05       0  4962.3    0.05       0
Bank Sta=4943.1,4962.3
Exp/Cntr=0.3,0.1

Type RM Length L Ch R = 1,44000,500,500,500
BEGIN DESCRIPTION:
BULLHEAD CREEK 88.0
END DESCRIPTION:
XS GIS Cut Line= 3
      2768681.41     10188798.53      2769587.71     10189599.18
      2770257.83     10190041.60
#Sta/Elev= 30
  3790.7 1335.11  3881.9 1334.92  3896.1 1332.79  3938.8 1338.62  3945.5 1337.90
  3953.0 1327.67  3959.7 1333.76  3967.3 1324.74  3973.9 1327.87  3981.5 1320.08
  3988.2 1321.83  3995.7 1317.73  4016.6 1314.28  4094.4 1307.54  4455.8 1302.92
  4662.9 1305.25  4875.3 1304.33  4909.2 1299.49  4966.1 1300.66  4984.8 1298.55
  4985.3 1295.55  5003.8 1295.55  5004.3 1298.55  5045.5 1299.45  5058.0 1302.69
  5103.2 1302.51  5124.3 1306.66  5289.8 1312.31  5377.1 1310.26  5803.0 1318.76
#Mann=5,-1,0
  3790.7    0.05       0  4662.9    0.12       0  4875.3    0.05       0
  4984.8    0.05       0  5004.3    0.05       0
Bank Sta=4984.8,5004.3
Exp/Cntr=0.3,0.1

Type RM Length L Ch R = 1,43500,500,500,500
BEGIN DESCRIPTION:
BULLHEAD CREEK 87.0
END DESCRIPTION:
XS GIS Cut Line= 3
      2768459.19     10188847.14      2769165.91     10189859.94
      2769625.88     10190194.38
#Sta/Elev= 30
  3765.0 1326.53  3802.7 1327.03  3945.7 1321.31  3967.4 1314.49  3981.5 1313.31
  4026.0 1315.59  4082.7 1311.85  4169.1 1313.28  4240.6 1305.77  4513.4 1305.39
  4572.3 1304.79  4665.6 1302.51  4723.0 1300.06  4787.2 1302.10  4789.2 1302.05
  4845.2 1299.33  4857.5 1301.46  4912.7 1303.18  4973.4 1301.73  4979.5 1296.84
  4989.1 1296.04  4989.6 1293.04  5008.1 1293.04  5008.6 1296.04  5024.4 1297.80
  5051.6 1296.61  5073.9 1299.40  5209.9 1301.75  5403.3 1312.77  5568.7 1315.41
#Mann=9,-1,0
  3765.0    0.05       0  4513.4    0.12       0  4572.3    0.05       0
  4665.6    0.12       0  4787.2    0.05       0  4789.2    0.12       0
  4912.7    0.05       0  4989.1    0.05       0  5008.6    0.05       0
Bank Sta=4989.1,5008.6
Exp/Cntr=0.3,0.1

Type RM Length L Ch R = 1,43000,500,500,500
BEGIN DESCRIPTION:
BULLHEAD CREEK 86.0
END DESCRIPTION:
XS GIS Cut Line= 3
      2767813.33     10189145.72      2768806.08     10190205.31
      2769205.69     10190453.11
#Sta/Elev= 30
  3548.0 1324.69  3569.2 1323.75  3576.0 1324.87  3583.4 1323.06  3597.5 1323.01
  3604.4 1324.42  3625.8 1321.89  3632.7 1322.79  3696.2 1320.59  3788.5 1315.75
  3951.2 1311.26  4028.8 1310.82  4156.3 1303.76  4484.5 1300.77  4514.1 1300.87
  4778.6 1300.56  4920.3 1298.01  4941.8 1295.07  4981.3 1292.93  4981.8 1289.93
  5000.4 1289.93  5000.9 1292.93  5047.9 1296.70  5078.6 1297.41  5121.1 1302.71
  5136.5 1301.38  5157.7 1304.22  5209.7 1305.72  5223.1 1307.77  5470.2 1315.33
#Mann=5,-1,0
  3548.0    0.05       0  4484.5    0.12       0  4514.1    0.05       0
  4981.3    0.05       0  5000.9    0.05       0
Bank Sta=4981.3,5000.9
Exp/Cntr=0.3,0.1

Type RM Length L Ch R = 1,42500,500,500,500
BEGIN DESCRIPTION:
BULLHEAD CREEK 85.0
END DESCRIPTION:
XS GIS Cut Line= 3
      2767755.68     10190053.11      2768476.73     10190579.60
      2769105.05     10190701.30
#Sta/Elev= 30
  4107.2 1350.12  4129.2 1344.58  4150.1 1343.73  4164.7 1338.30  4170.9 1343.27
  4179.4 1338.11  4185.6 1338.70  4193.9 1334.98  4200.3 1326.05  4206.5 1331.60
  4214.9 1321.25  4221.1 1325.67  4229.6 1317.47  4235.8 1320.39  4243.4 1311.73
  4279.8 1304.92  4357.1 1298.52  4409.8 1298.40  4441.2 1298.32  4567.9 1298.27
  4662.6 1297.79  4844.4 1296.55  4884.8 1292.08  4885.3 1289.08  4903.9 1289.08
  4904.4 1292.08  5049.9 1292.90  5101.6 1301.87  5243.4 1306.73  5640.0 1313.81
#Mann=7,-1,0
  4107.2    0.05       0  4409.8    0.12       0  4441.2    0.05       0
  4567.9    0.12       0  4662.6    0.05       0  4884.8    0.03       0
  4904.4    0.05       0
Bank Sta=4884.8,4904.4
Exp/Cntr=0.3,0.1

Type RM Length L Ch R = 1,42000,500,500,500
BEGIN DESCRIPTION:
BULLHEAD CREEK 84.0
END DESCRIPTION:
XS GIS Cut Line= 3
      2767705.67     10190053.08      2768109.94     10190915.09
      2768905.73     10190953.11
#Sta/Elev= 30
  4047.9 1350.40  4079.4 1349.46  4092.1 1347.31  4114.2 1348.23  4125.0 1344.20
  4147.3 1341.25  4244.7 1318.87  4273.0 1309.93  4279.9 1305.39  4295.8 1303.59
  4318.7 1298.05  4387.1 1296.25  4450.1 1297.82  4546.0 1297.07  4565.2 1296.82
  4672.0 1295.40  4700.4 1296.74  4776.9 1296.16  4860.1 1293.84  4882.9 1289.20
  4917.0 1289.80  4986.3 1288.69  4986.8 1285.69  5005.5 1285.69  5006.0 1288.69
  5045.8 1289.67  5175.9 1298.78  5346.1 1303.95  5396.2 1303.39  5796.7 1309.89
#Mann=7,-1,0
  4047.9    0.05       0  4450.1    0.12       0  4546.0    0.05       0
  4565.2    0.12       0  4917.0    0.05       0  4986.3    0.03       0
  5006.0    0.05       0
Bank Sta=4986.3,5006
Exp/Cntr=0.3,0.1

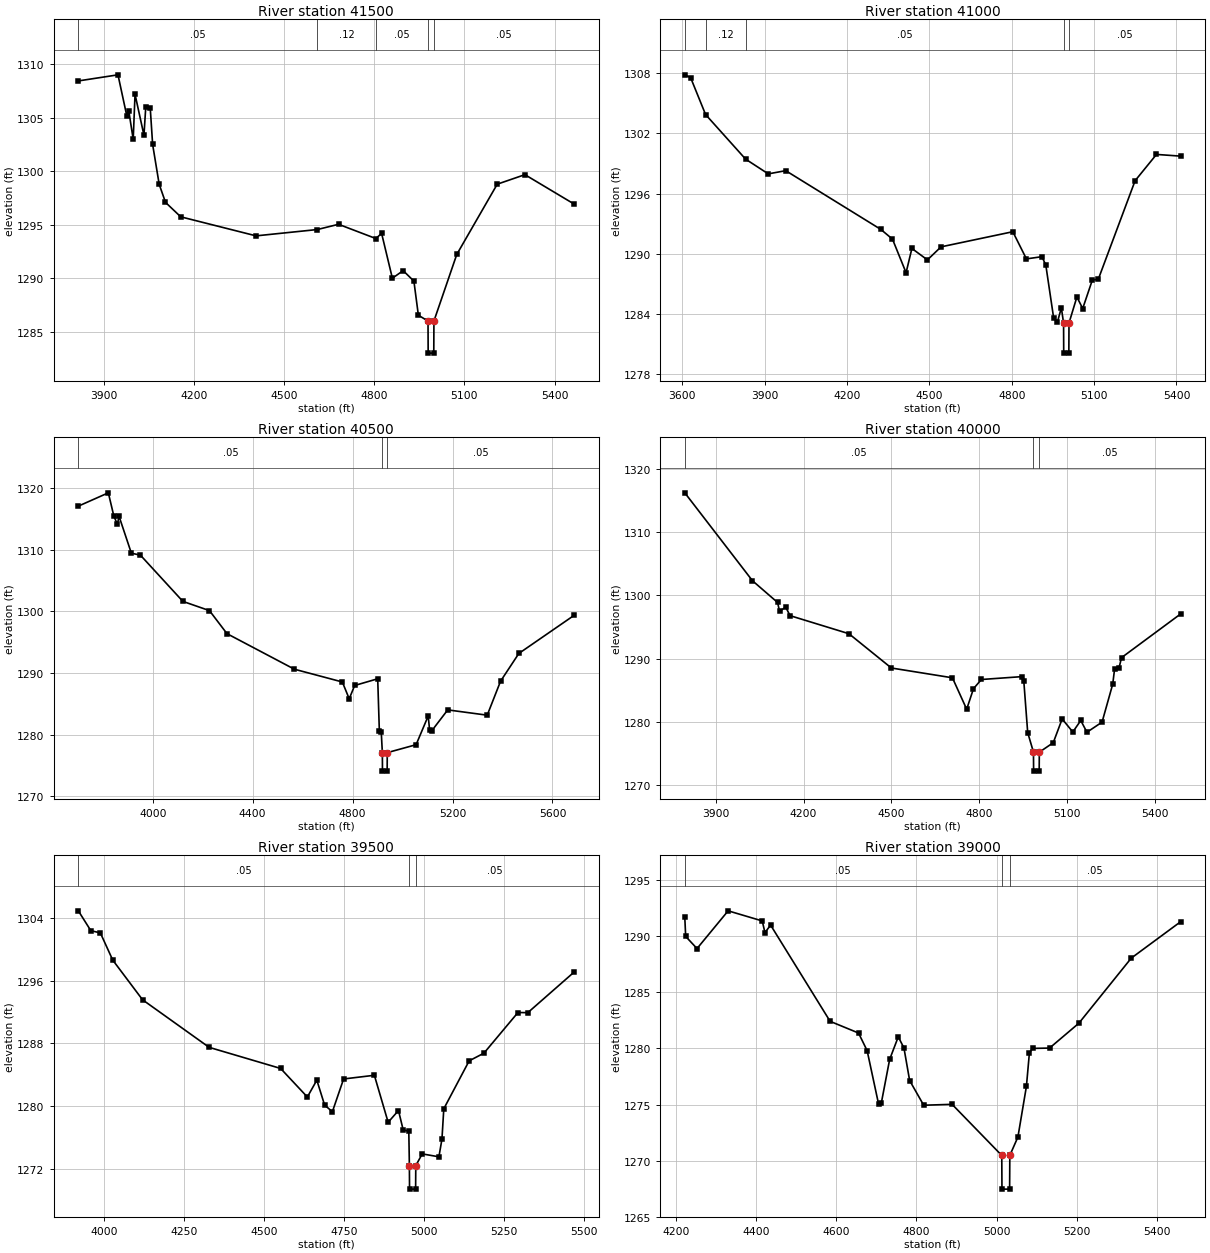
Type RM Length L Ch R = 1,41500,500,500,500
BEGIN DESCRIPTION:
BULLHEAD CREEK 83.0
END DESCRIPTION:
XS GIS Cut Line= 3
      2767125.87     10190319.39      2767798.42     10191295.65
      2768105.04     10191645.77
#Sta/Elev= 30
  3814.5 1308.42  3946.5 1308.99  3976.2 1305.11  3982.3 1305.65  3997.2 1302.96
  4003.3 1307.17  4033.0 1303.34  4039.1 1306.02  4054.0 1305.86  4061.9 1302.48
  4083.7 1298.76  4104.7 1297.07  4155.4 1295.72  4406.3 1293.94  4610.0 1294.53
  4680.9 1295.02  4805.1 1293.69  4824.3 1294.17  4860.1 1289.98  4896.0 1290.69
  4931.8 1289.71  4946.7 1286.52  4978.8 1285.98  4979.3 1282.98  4998.0 1282.98
  4998.5 1285.98  5074.5 1292.20  5209.3 1298.77  5301.4 1299.66  5465.4 1296.91
#Mann=5,-1,0
  3814.5    0.05       0  4610.0    0.12       0  4805.1    0.05       0
  4978.8    0.05       0  4998.5    0.05       0
Bank Sta=4978.8,4998.5
Exp/Cntr=0.3,0.1

Type RM Length L Ch R = 1,41000,500,500,500
BEGIN DESCRIPTION:
BULLHEAD CREEK 82.0
END DESCRIPTION:
XS GIS Cut Line= 3
      2766405.69     10190603.12      2767392.63     10191583.48
      2767685.22     10191878.07
#Sta/Elev= 30
  3608.9 1307.84  3630.1 1307.56  3684.6 1303.88  3830.4 1299.43  3913.0 1297.96
  3976.6 1298.28  4323.1 1292.42  4365.5 1291.45  4415.0 1288.10  4436.2 1290.52
  4492.8 1289.38  4542.3 1290.68  4803.9 1292.19  4853.4 1289.48  4910.0 1289.70
  4924.1 1288.86  4952.4 1283.63  4966.5 1283.19  4980.7 1284.60  4988.8 1283.08
  4989.3 1280.08  5008.0 1280.08  5008.5 1283.08  5037.3 1285.68  5058.5 1284.53
  5093.8 1287.39  5115.0 1287.43  5249.4 1297.28  5327.2 1299.90  5415.2 1299.73
#Mann=5,-1,0
  3608.9    0.05       0  3684.6    0.12       0  3830.4    0.05       0
  4988.8    0.05       0  5008.5    0.05       0
Bank Sta=4988.8,5008.5
Exp/Cntr=0.3,0.1

Type RM Length L Ch R = 1,40500,500,500,500
BEGIN DESCRIPTION:
BULLHEAD CREEK 81.0
END DESCRIPTION:
XS GIS Cut Line= 3
      2766005.68     10190703.11      2766987.76     10191551.68
      2767205.68     10192203.09
#Sta/Elev= 30
  3702.1 1317.08  3822.2 1319.24  3844.1 1315.49  3858.4 1314.13  3865.0 1315.44
  3914.4 1309.44  3950.5 1309.13  4120.6 1301.62  4227.0 1300.12  4297.2 1296.38
  4567.0 1290.61  4758.9 1288.54  4786.4 1285.81  4808.3 1287.97  4900.5 1289.06
  4907.1 1280.55  4914.7 1280.41  4919.1 1277.07  4919.6 1274.07  4938.3 1274.07
  4938.8 1277.07  5054.2 1278.36  5102.7 1283.03  5108.0 1280.81  5117.5 1280.65
  5180.8 1284.01  5338.9 1283.15  5392.2 1288.66  5465.5 1293.17  5686.9 1299.36
#Mann=3,-1,0
  3702.1    0.05       0  4919.1    0.03       0  4938.8    0.05       0
Bank Sta=4919.1,4938.8
Exp/Cntr=0.3,0.1

Type RM Length L Ch R = 1,40000,500,500,500
BEGIN DESCRIPTION:
BULLHEAD CREEK 80.0
END DESCRIPTION:
XS GIS Cut Line= 3
      2766005.69     10190853.11      2766693.39     10191842.84
      2766955.66     10192253.07
#Sta/Elev= 30
  3794.8 1316.24  4025.7 1302.32  4111.4 1298.88  4118.2 1297.48  4139.2 1298.14
  4154.0 1296.79  4354.9 1293.93  4499.8 1288.50  4708.1 1286.95  4756.8 1281.97
  4780.0 1285.23  4807.0 1286.68  4944.1 1287.13  4951.6 1286.50  4965.0 1278.28
  4984.7 1275.17  4985.2 1272.17  5004.2 1272.17  5004.7 1275.17  5052.2 1276.67
  5082.6 1280.43  5119.0 1278.37  5146.1 1280.19  5167.2 1278.33  5218.8 1279.93
  5255.2 1285.95  5261.4 1288.29  5276.3 1288.45  5285.2 1290.14  5486.9 1297.06
#Mann=3,-1,0
  3794.8    0.05       0  4984.7    0.03       0  5004.7    0.05       0
Bank Sta=4984.7,5004.7
Exp/Cntr=0.3,0.1

Type RM Length L Ch R = 1,39500,500,500,500
BEGIN DESCRIPTION:
BULLHEAD CREEK 79.0
END DESCRIPTION:
XS GIS Cut Line= 3
      2765955.69     10191203.12      2766355.06     10192206.24
      2766755.70     10192453.12
#Sta/Elev= 30
  3920.3 1304.89  3959.4 1302.36  3989.1 1302.08  4027.9 1298.61  4121.2 1293.55
  4329.3 1287.49  4552.8 1284.80  4636.4 1281.16  4666.0 1283.31  4690.3 1280.14
  4714.6 1279.28  4749.7 1283.46  4845.9 1283.93  4889.0 1277.94  4921.3 1279.44
  4935.8 1277.00  4953.6 1276.77  4955.4 1272.42  4955.9 1269.42  4974.9 1269.42
  4975.4 1272.42  4995.6 1273.91  5047.7 1273.54  5057.2 1275.78  5063.0 1279.66
  5142.3 1285.77  5188.5 1286.75  5294.9 1291.93  5325.7 1291.91  5470.6 1297.09
#Mann=3,-1,0
  3920.3    0.05       0  4955.4    0.05       0  4975.4    0.05       0
Bank Sta=4955.4,4975.4
Exp/Cntr=0.3,0.1

Type RM Length L Ch R = 1,39000,500,500,500
BEGIN DESCRIPTION:
BULLHEAD CREEK 78.0
END DESCRIPTION:
XS GIS Cut Line= 3
      2765438.37     10191937.43      2765966.10     10192509.35
      2766355.72     10192753.13
#Sta/Elev= 30
  4221.8 1291.66  4224.0 1289.97  4252.3 1288.89  4330.0 1292.25  4415.1 1291.35
  4421.9 1290.31  4436.0 1290.98  4584.6 1282.41  4655.5 1281.37  4677.0 1279.80
  4705.4 1275.07  4712.2 1275.10  4733.2 1279.02  4754.7 1281.03  4768.9 1280.04
  4783.1 1277.14  4818.2 1274.94  4889.1 1275.02  5013.1 1270.47  5013.6 1267.47
  5032.7 1267.47  5033.2 1270.47  5053.4 1272.11  5074.6 1276.61  5082.1 1279.61
  5090.0 1280.00  5132.4 1280.03  5205.5 1282.24  5336.4 1288.04  5459.6 1291.28
#Mann=3,-1,0
  4221.8    0.05       0  5013.1    0.05       0  5033.2    0.05       0
Bank Sta=5013.1,5033.2
Exp/Cntr=0.3,0.1

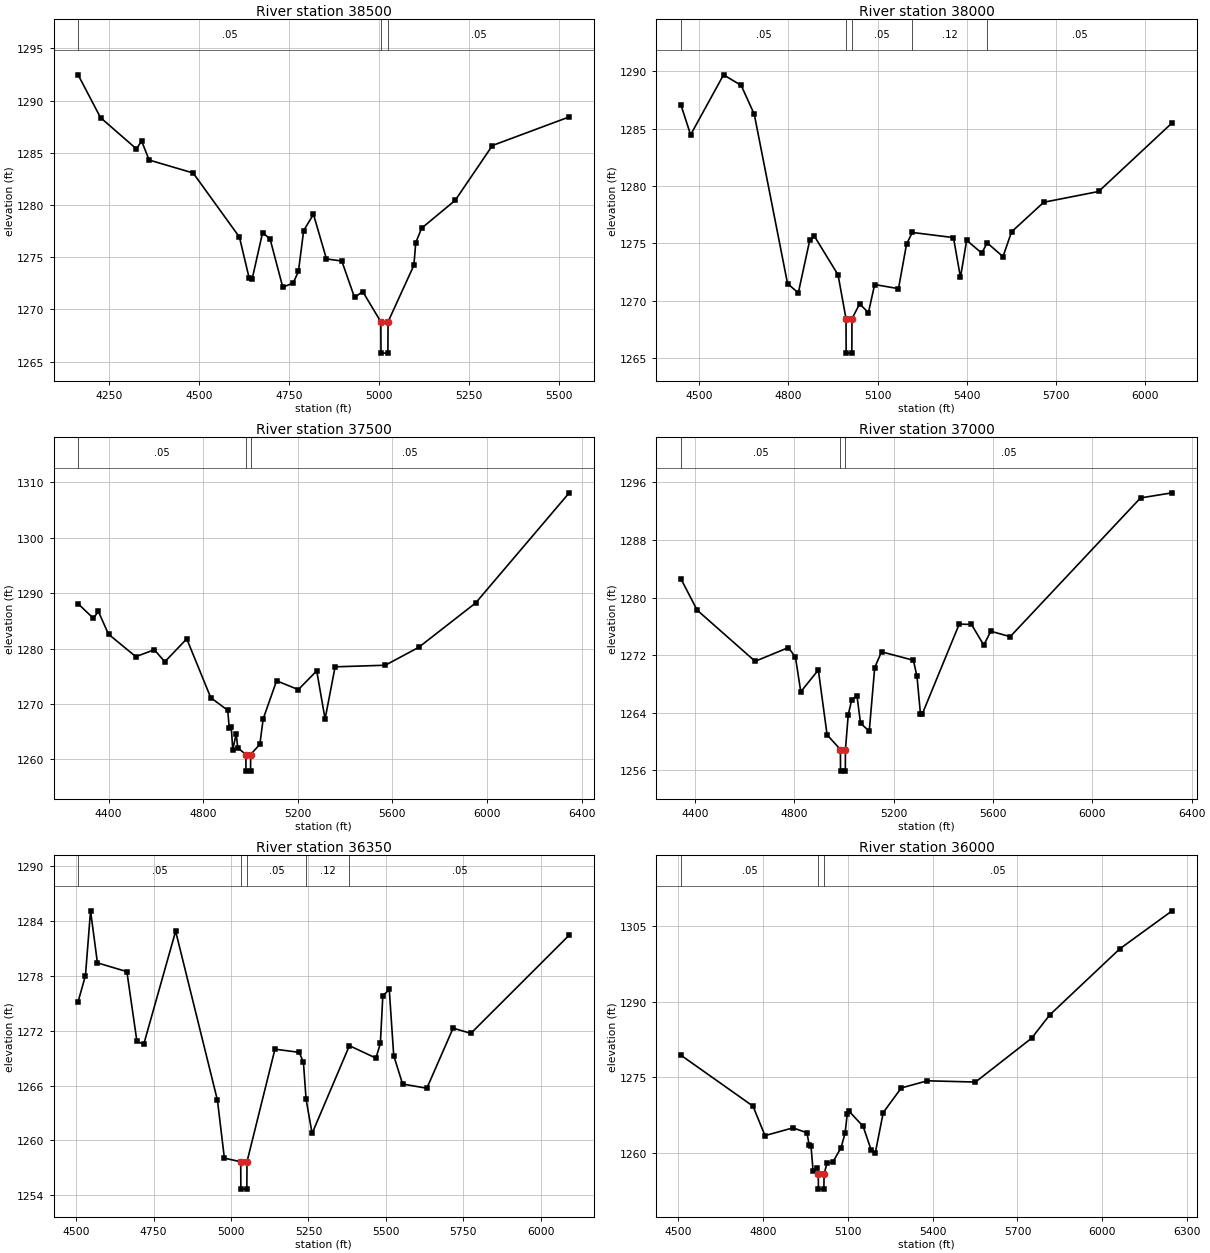
Type RM Length L Ch R = 1,38500,500,500,500
BEGIN DESCRIPTION:
BULLHEAD CREEK 77.0
END DESCRIPTION:
XS GIS Cut Line= 3
      2764980.01     10192361.02      2765641.56     10192872.63
      2766152.12     10193006.46
#Sta/Elev= 30
  4163.7 1292.46  4226.0 1288.36  4325.7 1285.37  4340.1 1286.12  4361.0 1284.30
  4483.2 1283.06  4611.8 1276.92  4639.0 1272.97  4647.1 1272.90  4676.1 1277.35
  4696.9 1276.74  4732.2 1272.12  4761.2 1272.53  4775.7 1273.64  4790.2 1277.55
  4817.4 1279.10  4853.5 1274.83  4896.1 1274.63  4931.5 1271.14  4954.1 1271.71
  5004.5 1268.81  5005.0 1265.81  5024.1 1265.81  5024.6 1268.81  5096.3 1274.22
  5101.5 1276.39  5118.0 1277.78  5211.0 1280.44  5314.4 1285.69  5527.8 1288.43
#Mann=3,-1,0
  4163.7    0.05       0  5004.5    0.05       0  5024.6    0.05       0
Bank Sta=5004.5,5024.6
Exp/Cntr=0.3,0.1

Type RM Length L Ch R = 1,38000,500,500,500
BEGIN DESCRIPTION:
BULLHEAD CREEK 76.0
END DESCRIPTION:
XS GIS Cut Line= 3
      2764986.96     10192666.57      2765250.54     10193162.25
      2765875.82     10194055.43
#Sta/Elev= 30
  4438.6 1287.08  4471.1 1284.47  4581.9 1289.70  4641.2 1288.78  4685.2 1286.26
  4797.1 1271.50  4833.3 1270.69  4871.6 1275.27  4887.7 1275.62  4967.0 1272.26
  4993.7 1268.44  4994.2 1265.44  5013.3 1265.44  5013.8 1268.44  5039.5 1269.73
  5069.1 1268.97  5090.0 1271.42  5170.2 1271.06  5197.3 1274.94  5216.6 1275.96
  5355.1 1275.51  5378.6 1272.04  5399.5 1275.28  5450.1 1274.16  5468.6 1275.05
  5521.6 1273.85  5550.4 1276.01  5658.5 1278.59  5843.3 1279.53  6090.3 1285.51
#Mann=5,-1,0
  4438.6    0.05       0  4993.7    0.03       0  5013.8    0.05       0
  5216.6    0.12       0  5468.6    0.05       0
Bank Sta=4993.7,5013.8
Exp/Cntr=0.3,0.1

Type RM Length L Ch R = 1,37500,500,500,500
BEGIN DESCRIPTION:
BULLHEAD CREEK 75.0
END DESCRIPTION:
XS GIS Cut Line= 3
      2764632.82     10193006.89      2765043.92     10193608.56
      2766005.66     10194553.09
#Sta/Elev= 30
  4271.3 1288.10  4335.9 1285.48  4356.9 1286.72  4399.9 1282.61  4515.3 1278.56
  4593.7 1279.80  4637.9 1277.63  4730.7 1281.77  4832.3 1271.15  4904.1 1268.87
  4910.2 1265.74  4919.0 1265.91  4925.1 1261.77  4940.0 1264.63  4946.1 1262.12
  4980.7 1260.90  4981.2 1257.90  5000.5 1257.90  5001.0 1260.90  5039.8 1262.74
  5054.0 1267.35  5110.6 1274.20  5202.4 1272.61  5280.3 1275.99  5315.6 1267.30
  5358.0 1276.72  5570.2 1277.01  5711.6 1280.24  5952.1 1288.24  6348.0 1308.12
#Mann=3,-1,0
  4271.3    0.05       0  4980.7    0.03       0  5001.0    0.05       0
Bank Sta=4980.7,5001
Exp/Cntr=0.3,0.1

Type RM Length L Ch R = 1,37000,650,650,650
BEGIN DESCRIPTION:
BULLHEAD CREEK 74.0
END DESCRIPTION:
XS GIS Cut Line= 3
      2764167.50     10193388.78      2764637.18     10193848.32
      2765493.92     10194854.09
#Sta/Elev= 30
  4342.9 1282.60  4408.4 1278.25  4641.7 1271.15  4776.0 1273.06  4804.3 1271.69
  4825.6 1266.92  4896.3 1269.94  4931.6 1260.93  4985.2 1258.89  4985.7 1255.89
  5005.0 1255.89  5005.5 1258.89  5016.8 1263.74  5031.1 1265.83  5052.0 1266.35
  5066.2 1262.55  5101.4 1261.44  5123.4 1270.28  5150.8 1272.47  5279.3 1271.29
  5293.6 1269.06  5307.8 1263.77  5314.4 1263.78  5463.8 1276.32  5513.2 1276.27
  5562.6 1273.40  5591.1 1275.33  5669.1 1274.57  6194.0 1293.85  6321.2 1294.56
#Mann=3,-1,0
  4342.9    0.05       0  4985.2    0.05       0  5005.5    0.05       0
Bank Sta=4985.2,5005.5
Exp/Cntr=0.3,0.1

Type RM Length L Ch R = 1,36350,350,350,350
BEGIN DESCRIPTION:
BULLHEAD CREEK 73.0
END DESCRIPTION:
XS GIS Cut Line= 3
      2763785.60     10194069.37      2764224.50     10194295.00
      2765070.30     10194986.03
#Sta/Elev= 30
  4506.5 1275.19  4530.2 1278.04  4546.7 1285.14  4568.9 1279.44  4664.0 1278.48
  4696.4 1270.85  4718.5 1270.53  4821.4 1282.91  4956.4 1264.39  4978.8 1258.05
  5031.5 1257.66  5032.0 1254.66  5051.3 1254.66  5051.8 1257.66  5142.1 1269.99
  5220.4 1269.64  5234.0 1268.55  5242.6 1264.50  5262.0 1260.76  5382.4 1270.37
  5468.1 1269.01  5482.4 1270.62  5490.3 1275.83  5511.1 1276.53  5525.5 1269.29
  5554.2 1266.17  5632.5 1265.71  5717.2 1272.29  5774.6 1271.72  6092.2 1282.48
#Mann=5,-1,0
  4506.5    0.05       0  5031.5    0.05       0  5051.8    0.05       0
  5242.6    0.12       0  5382.4    0.05       0
Bank Sta=5031.5,5051.8
Exp/Cntr=0.3,0.1

Type RM Length L Ch R = 1,36000,500,500,500
BEGIN DESCRIPTION:
BULLHEAD CREEK 72.0
END DESCRIPTION:
XS GIS Cut Line= 3
      2763805.69     10194303.11      2764161.16     10194639.49
      2765105.66     10195453.09
#Sta/Elev= 30
  4510.6 1279.36  4765.3 1269.26  4807.7 1263.42  4906.8 1264.96  4956.2 1263.97
  4963.5 1261.60  4970.4 1261.29  4977.6 1256.48  4991.8 1256.99  4996.1 1255.81
  4996.6 1252.81  5015.9 1252.81  5016.4 1255.81  5027.1 1257.96  5048.0 1258.22
  5076.5 1261.02  5090.8 1263.93  5098.4 1267.68  5105.0 1268.24  5154.4 1265.28
  5182.9 1260.58  5197.2 1259.88  5225.7 1268.00  5289.4 1272.87  5381.5 1274.29
  5551.6 1274.04  5750.2 1282.74  5813.8 1287.33  6061.9 1300.46  6246.6 1307.99
#Mann=3,-1,0
  4510.6    0.05       0  4996.1    0.05       0  5016.4    0.05       0
Bank Sta=4996.1,5016.4
Exp/Cntr=0.3,0.1