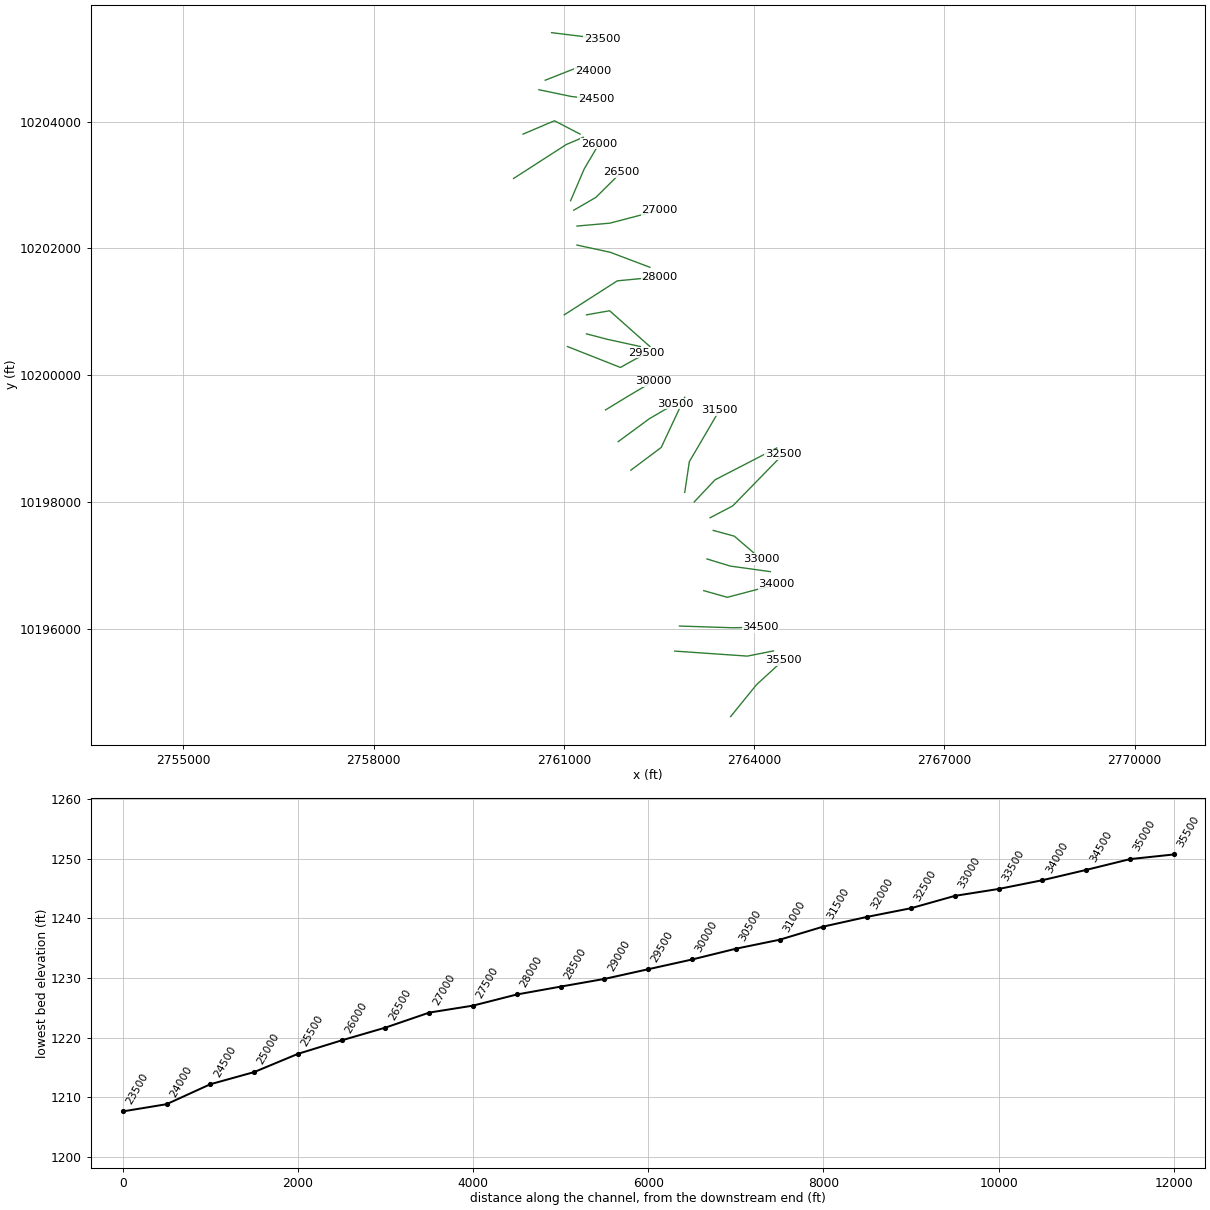
HEC-RAS study BULLHEAD CREEK.prj: BULLHEAD CREEK Base Level Engineering

--- BULLHEAD CREEK.g01 (geometry) --- (continued)

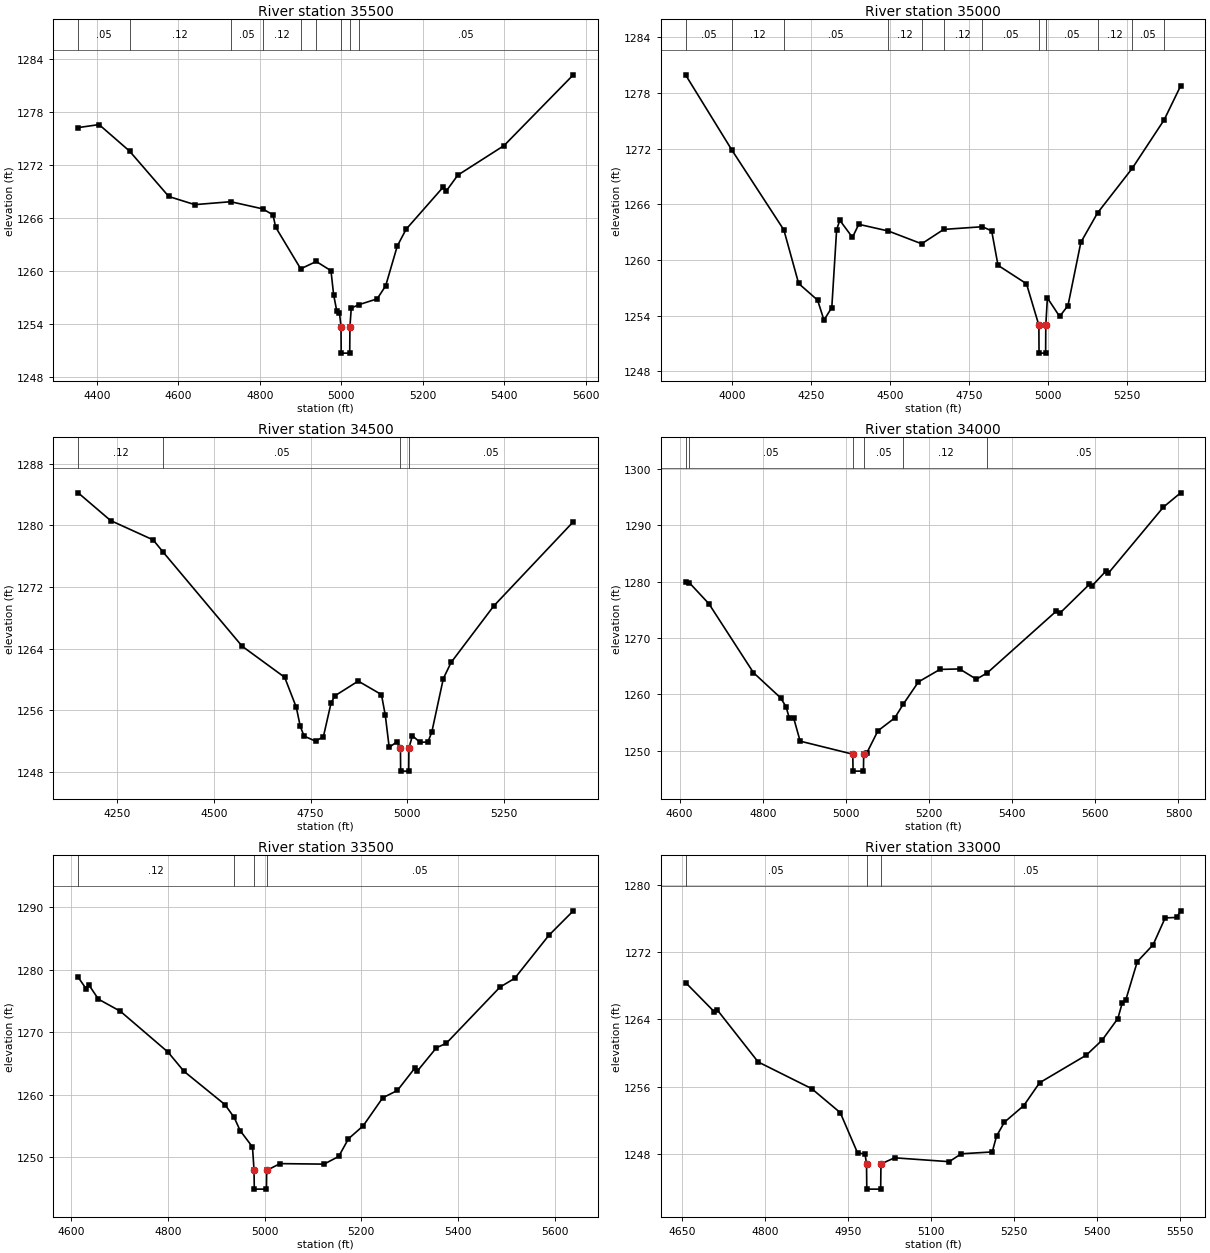
Type RM Length L Ch R = 1,35500,500,500,500
BEGIN DESCRIPTION:
BULLHEAD CREEK 71.0
END DESCRIPTION:
XS GIS Cut Line= 3
      2763629.34     10194617.12      2764036.08     10195118.86
      2764455.71     10195503.14
#Sta/Elev= 30
  4354.1 1276.20  4405.4 1276.54  4480.1 1273.55  4576.4 1268.42  4640.3 1267.50
  4728.4 1267.83  4807.1 1267.02  4832.2 1266.34  4838.6 1264.96  4900.1 1260.25
  4938.2 1261.08  4974.4 1260.04  4980.9 1257.33  4988.8 1255.45  4995.2 1255.30
  4999.0 1253.73  4999.5 1250.73  5020.4 1250.73  5020.9 1253.73  5024.2 1255.82
  5042.3 1256.19  5087.7 1256.86  5108.6 1258.33  5137.0 1262.81  5158.6 1264.71
  5250.5 1269.52  5257.2 1269.03  5285.6 1270.83  5399.1 1274.17  5569.0 1282.16
#Mann=9,-1,0
  4354.1    0.05       0  4480.1    0.12       0  4728.4    0.05       0
  4807.1    0.12       0  4900.1    0.05       0  4938.2    0.12       0
  4999.0    0.07       0  5020.9    0.12       0  5042.3    0.05       0
Bank Sta=4999,5020.9
Exp/Cntr=0.3,0.1

Type RM Length L Ch R = 1,35000,500,500,500
BEGIN DESCRIPTION:
BULLHEAD CREEK 70.0
END DESCRIPTION:
XS GIS Cut Line= 3
      2762748.27     10195650.08      2763892.74     10195570.90
      2764305.73     10195653.12
#Sta/Elev= 30
  3852.8 1279.96  4000.3 1271.81  4164.3 1263.23  4211.1 1257.46  4271.2 1255.66
  4291.3 1253.51  4316.1 1254.87  4331.4 1263.25  4341.4 1264.28  4381.5 1262.43
  4401.5 1263.84  4495.0 1263.12  4600.8 1261.74  4670.5 1263.29  4792.8 1263.58
  4822.5 1263.13  4842.6 1259.42  4932.8 1257.43  4972.0 1252.95  4972.5 1249.95
  4993.4 1249.95  4993.9 1252.95  4999.0 1255.90  5037.8 1253.90  5064.2 1255.08
  5105.0 1261.90  5157.9 1265.07  5267.6 1269.87  5368.9 1275.11  5421.1 1278.77
#Mann=12,-1,0
  3852.8    0.05       0  4000.3    0.12       0  4164.3    0.05       0
  4495.0    0.12       0  4600.8    0.05       0  4670.5    0.12       0
  4792.8    0.05       0  4972.0    0.03       0  4993.9    0.05       0
  5157.9    0.12       0  5267.6    0.05       0  5368.9    0.12       0
Bank Sta=4972,4993.9
Exp/Cntr=0.3,0.1

Type RM Length L Ch R = 1,34500,500,500,500
BEGIN DESCRIPTION:
BULLHEAD CREEK 69.0
END DESCRIPTION:
XS GIS Cut Line= 3
      2762822.01     10196045.05      2763672.27     10196017.62
      2764101.55     10196027.67
#Sta/Elev= 30
  4149.3 1284.21  4233.0 1280.62  4343.1 1278.11  4368.6 1276.55  4573.2 1264.33
  4683.2 1260.30  4713.3 1256.40  4723.3 1253.98  4733.3 1252.68  4763.3 1252.02
  4783.3 1252.61  4803.3 1257.01  4813.3 1257.91  4873.3 1259.81  4933.4 1258.06
  4943.4 1255.35  4953.4 1251.22  4973.4 1251.94  4982.5 1251.14  4983.0 1248.14
  5003.9 1248.14  5004.4 1251.14  5013.4 1252.72  5033.4 1251.87  5053.4 1251.92
  5063.4 1253.16  5093.4 1260.14  5113.4 1262.22  5223.5 1269.53  5429.4 1280.46
#Mann=4,-1,0
  4149.3    0.12       0  4368.6    0.05       0  4982.5    0.03       0
  5004.4    0.05       0
Bank Sta=4982.5,5004.4
Exp/Cntr=0.3,0.1

Type RM Length L Ch R = 1,34000,500,500,500
BEGIN DESCRIPTION:
BULLHEAD CREEK 68.0
END DESCRIPTION:
XS GIS Cut Line= 3
      2763205.68     10196603.11      2763576.87     10196498.33
      2764355.70     10196703.12
#Sta/Elev= 30
  4614.3 1279.98  4623.1 1279.81  4670.5 1276.06  4777.7 1263.85  4842.9 1259.40
  4856.0 1257.83  4863.7 1255.87  4874.1 1255.90  4890.0 1251.72  5016.7 1249.41
  5017.2 1246.41  5042.3 1246.41  5042.8 1249.41  5050.5 1249.65  5077.1 1253.55
  5117.4 1255.82  5138.5 1258.32  5174.6 1262.22  5226.3 1264.43  5273.6 1264.51
  5313.9 1262.69  5340.4 1263.83  5505.3 1274.70  5515.8 1274.46  5586.0 1279.52
  5591.2 1279.16  5626.3 1281.90  5631.5 1281.48  5763.9 1293.19  5805.3 1295.71
#Mann=6,-1,0
  4614.3    0.12       0  4623.1    0.05       0  5016.7    0.03       0
  5042.8    0.05       0  5138.5    0.12       0  5340.4    0.05       0
Bank Sta=5016.7,5042.8
Exp/Cntr=0.3,0.1

Type RM Length L Ch R = 1,33500,500,500,500
BEGIN DESCRIPTION:
BULLHEAD CREEK 67.0
END DESCRIPTION:
XS GIS Cut Line= 3
      2763255.70     10197103.11      2763623.92     10196990.69
      2764255.68     10196903.11
#Sta/Elev= 30
  4615.0 1278.83  4631.4 1277.00  4636.6 1277.67  4656.8 1275.33  4702.2 1273.39
  4800.7 1266.85  4833.5 1263.79  4918.2 1258.46  4937.3 1256.40  4949.6 1254.30
  4975.1 1251.68  4978.3 1247.94  4978.8 1244.94  5003.9 1244.94  5004.4 1247.94
  5032.1 1249.02  5122.9 1248.94  5153.2 1250.17  5173.4 1253.00  5203.7 1255.06
  5244.1 1259.55  5274.4 1260.72  5309.9 1264.25  5314.9 1263.76  5355.1 1267.56
  5375.3 1268.26  5486.4 1277.26  5516.7 1278.66  5587.3 1285.54  5637.8 1289.46
#Mann=4,-1,0
  4615.0    0.12       0  4937.3    0.05       0  4978.3    0.03       0
  5004.4    0.05       0
Bank Sta=4978.3,5004.4
Exp/Cntr=0.3,0.1

Type RM Length L Ch R = 1,33000,500,500,500
BEGIN DESCRIPTION:
BULLHEAD CREEK 66.0
END DESCRIPTION:
XS GIS Cut Line= 3
      2763355.67     10197553.12      2763687.44     10197462.60
      2764105.68     10197103.12
#Sta/Elev= 30
  4656.1 1268.39  4707.9 1264.92  4713.1 1265.16  4787.4 1258.93  4884.2 1255.75
  4935.9 1252.89  4967.1 1248.11  4980.8 1247.95  4983.4 1246.78  4983.9 1243.78
  5009.0 1243.78  5009.5 1246.78  5034.1 1247.51  5132.9 1247.05  5154.8 1247.99
  5210.8 1248.21  5218.5 1250.09  5232.7 1251.75  5267.8 1253.73  5296.4 1256.45
  5380.9 1259.74  5409.4 1261.52  5437.9 1264.10  5445.6 1265.90  5452.2 1266.30
  5473.1 1270.88  5501.6 1272.88  5523.5 1276.09  5544.4 1276.14  5551.5 1276.93
#Mann=3,-1,0
  4656.1    0.05       0  4983.4    0.03       0  5009.5    0.05       0
Bank Sta=4983.4,5009.5
Exp/Cntr=0.3,0.1

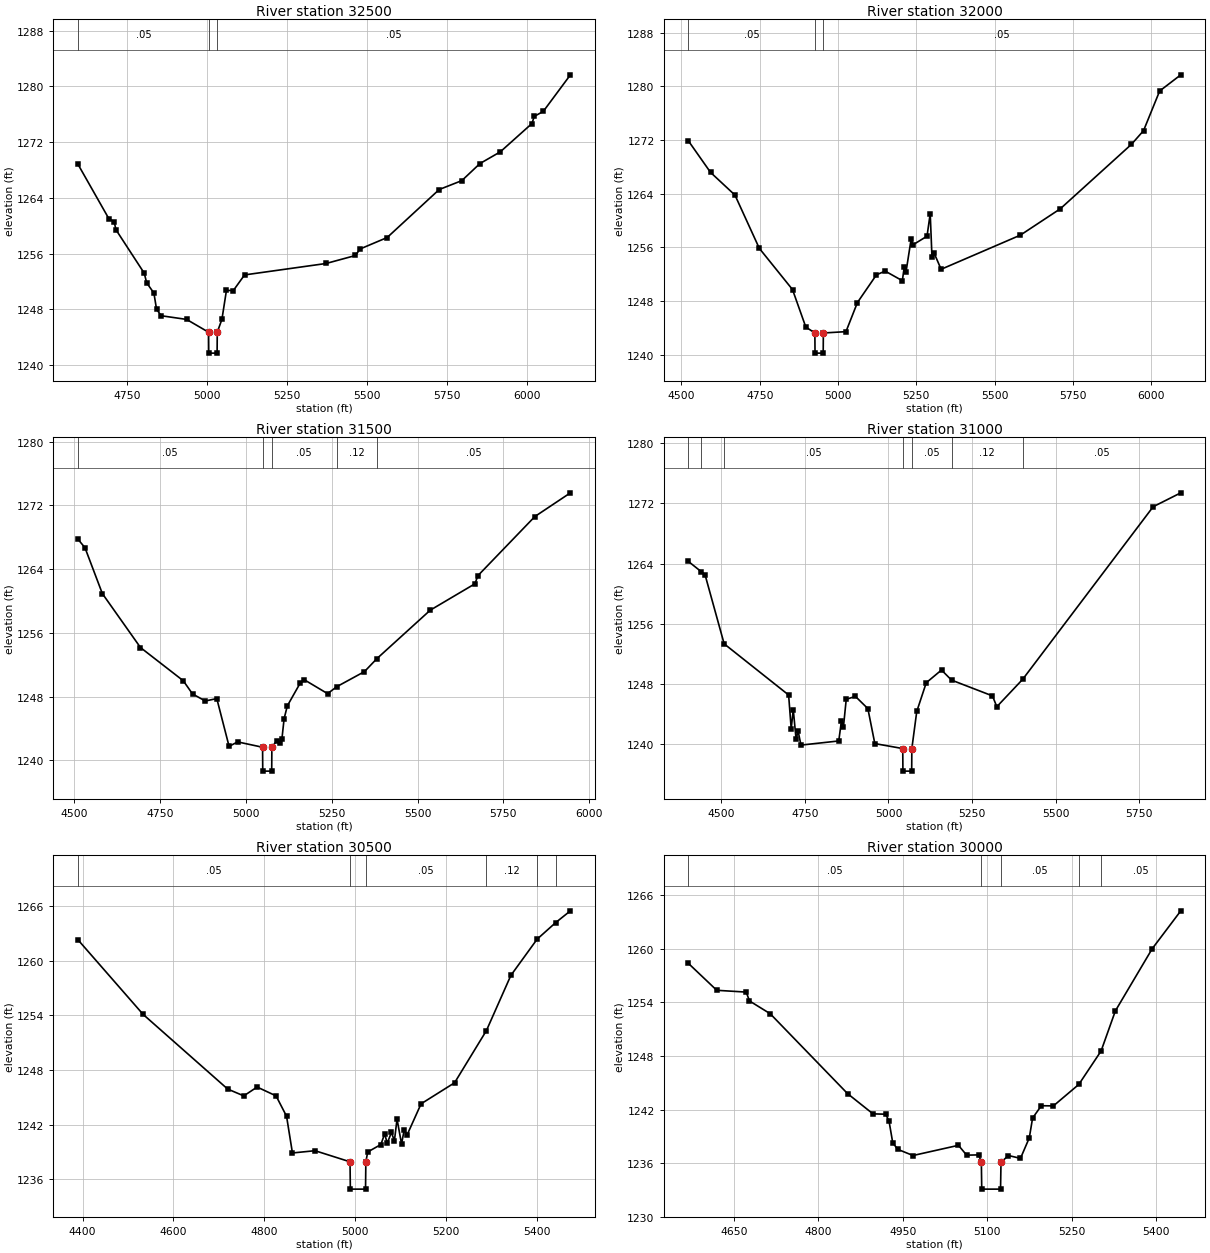
Type RM Length L Ch R = 1,32500,500,500,500
BEGIN DESCRIPTION:
BULLHEAD CREEK 65.0
END DESCRIPTION:
XS GIS Cut Line= 3
      2763305.64     10197753.09      2763663.45     10197940.46
      2764455.67     10198753.10
#Sta/Elev= 30
  4596.1 1268.81  4692.6 1261.00  4709.0 1260.57  4714.7 1259.42  4803.0 1253.19
  4810.6 1251.81  4833.2 1250.33  4841.4 1248.03  4855.8 1247.08  4935.4 1246.55
  5004.1 1244.71  5004.6 1241.71  5030.7 1241.71  5031.2 1244.71  5045.8 1246.57
  5059.9 1250.72  5081.3 1250.69  5116.5 1252.94  5371.1 1254.58  5463.2 1255.73
  5477.3 1256.66  5562.2 1258.31  5724.8 1265.20  5795.5 1266.48  5852.1 1268.93
  5915.7 1270.61  6014.7 1274.68  6021.8 1275.70  6050.1 1276.42  6134.9 1281.67
#Mann=3,-1,0
  4596.1    0.05       0  5004.1    0.03       0  5031.2    0.05       0
Bank Sta=5004.1,5031.2
Exp/Cntr=0.3,0.1

Type RM Length L Ch R = 1,32000,500,500,500
BEGIN DESCRIPTION:
BULLHEAD CREEK 64.0
END DESCRIPTION:
XS GIS Cut Line= 3
      2763055.69     10198003.12      2763383.23     10198350.98
      2764355.65     10198853.10
#Sta/Elev= 30
  4522.2 1271.88  4592.8 1267.19  4670.9 1263.80  4748.6 1255.87  4854.6 1249.73
  4897.0 1244.15  4926.0 1243.26  4926.5 1240.26  4952.6 1240.26  4953.1 1243.26
  5025.3 1243.46  5061.9 1247.80  5122.7 1251.93  5150.5 1252.48  5205.3 1251.05
  5211.3 1253.05  5217.0 1252.34  5233.5 1257.28  5239.1 1256.39  5284.1 1257.68
  5294.3 1261.05  5299.9 1254.58  5306.6 1255.18  5329.1 1252.75  5582.3 1257.84
  5709.6 1261.76  5936.9 1271.37  5975.4 1273.40  6026.9 1279.31  6094.4 1281.72
#Mann=3,-1,0
  4522.2    0.05       0  4926.0    0.03       0  4953.1    0.05       0
Bank Sta=4926,4953.1
Exp/Cntr=0.3,0.1

Type RM Length L Ch R = 1,31500,500,500,500
BEGIN DESCRIPTION:
BULLHEAD CREEK 63.0
END DESCRIPTION:
XS GIS Cut Line= 3
      2762905.68     10198153.11      2762977.89     10198637.15
      2763455.71     10199453.15
#Sta/Elev= 30
  4510.6 1267.74  4530.8 1266.69  4581.4 1260.93  4692.6 1254.15  4817.3 1249.98
  4844.3 1248.32  4881.5 1247.44  4915.0 1247.74  4950.8 1241.74  4975.7 1242.30
  5048.4 1241.63  5048.9 1238.63  5075.0 1238.63  5075.5 1241.63  5089.3 1242.43
  5099.1 1242.13  5104.9 1242.72  5111.2 1245.22  5120.6 1246.83  5157.6 1249.65
  5169.4 1250.12  5237.9 1248.36  5264.5 1249.23  5345.4 1251.13  5381.4 1252.75
  5537.0 1258.84  5667.4 1262.16  5675.8 1263.17  5841.9 1270.60  5945.6 1273.58
#Mann=5,-1,0
  4510.6    0.05       0  5048.4    0.03       0  5075.5    0.05       0
  5264.5    0.12       0  5381.4    0.05       0
Bank Sta=5048.4,5075.5
Exp/Cntr=0.3,0.1

Type RM Length L Ch R = 1,31000,500,500,500
BEGIN DESCRIPTION:
BULLHEAD CREEK 62.0
END DESCRIPTION:
XS GIS Cut Line= 3
      2762055.69     10198503.12      2762534.69     10198861.45
      2762905.69     10199653.13
#Sta/Elev= 30
  4401.8 1264.29  4440.5 1262.92  4451.7 1262.50  4508.7 1253.34  4701.5 1246.54
  4709.2 1242.06  4715.4 1244.59  4723.8 1240.67  4730.0 1241.72  4738.4 1239.88
  4851.4 1240.43  4859.3 1243.02  4865.5 1242.32  4873.8 1245.97  4901.3 1246.35
  4938.5 1244.73  4959.3 1240.08  5042.8 1239.42  5043.3 1236.42  5069.5 1236.42
  5070.0 1239.42  5084.7 1244.35  5113.1 1248.17  5158.7 1249.86  5188.6 1248.52
  5311.1 1246.42  5324.1 1244.98  5401.6 1248.63  5791.6 1271.56  5874.3 1273.41
#Mann=7,-1,0
  4401.8    0.05       0  4440.5    0.12       0  4508.7    0.05       0
  5042.8    0.03       0  5070.0    0.05       0  5188.6    0.12       0
  5401.6    0.05       0
Bank Sta=5042.8,5070
Exp/Cntr=0.3,0.1

Type RM Length L Ch R = 1,30500,500,500,500
BEGIN DESCRIPTION:
BULLHEAD CREEK 61.0
END DESCRIPTION:
XS GIS Cut Line= 3
      2761855.68     10198953.11      2762347.11     10199314.32
      2762755.66     10199553.09
#Sta/Elev= 30
  4390.1 1262.28  4533.2 1254.10  4719.2 1245.90  4754.7 1245.15  4784.0 1246.12
  4825.7 1245.15  4848.8 1242.91  4861.7 1238.88  4911.4 1239.13  4988.4 1237.91
  4989.1 1234.91  5022.5 1234.91  5023.2 1237.91  5027.3 1238.99  5056.3 1239.81
  5064.5 1240.98  5070.3 1239.95  5079.4 1241.14  5086.0 1240.22  5091.8 1242.60
  5101.7 1239.87  5107.5 1241.39  5114.2 1240.89  5144.7 1244.28  5218.4 1246.59
  5288.4 1252.32  5342.2 1258.38  5400.0 1262.36  5440.8 1264.18  5473.2 1265.47
#Mann=6,-1,0
  4390.1    0.05       0  4988.4    0.03       0  5023.2    0.05       0
  5288.4    0.12       0  5400.0    0.05       0  5440.8    0.12       0
Bank Sta=4988.4,5023.2
Exp/Cntr=0.3,0.1

Type RM Length L Ch R = 1,30000,500,500,500
BEGIN DESCRIPTION:
BULLHEAD CREEK 60.0
END DESCRIPTION:
XS GIS Cut Line= 3
      2761655.66     10199453.10      2762023.66     10199677.26
      2762405.69     10199903.12
#Sta/Elev= 30
  4569.1 1258.35  4619.5 1255.34  4671.8 1255.14  4677.6 1254.15  4714.4 1252.72
  4851.9 1243.78  4897.0 1241.52  4919.6 1241.48  4925.5 1240.71  4932.1 1238.28
  4941.0 1237.55  4968.1 1236.86  5048.8 1238.00  5063.4 1236.90  5084.9 1236.93
  5089.5 1236.10  5090.2 1233.10  5123.6 1233.10  5124.4 1236.10  5137.6 1236.86
  5159.0 1236.54  5174.7 1238.84  5180.5 1241.05  5196.1 1242.43  5217.5 1242.41
  5262.6 1244.81  5302.2 1248.55  5327.6 1253.04  5393.1 1260.00  5443.8 1264.23
#Mann=5,-1,0
  4569.1    0.05       0  5089.5    0.03       0  5124.4    0.05       0
  5262.6    0.12       0  5302.2    0.05       0
Bank Sta=5089.5,5124.4
Exp/Cntr=0.3,0.1

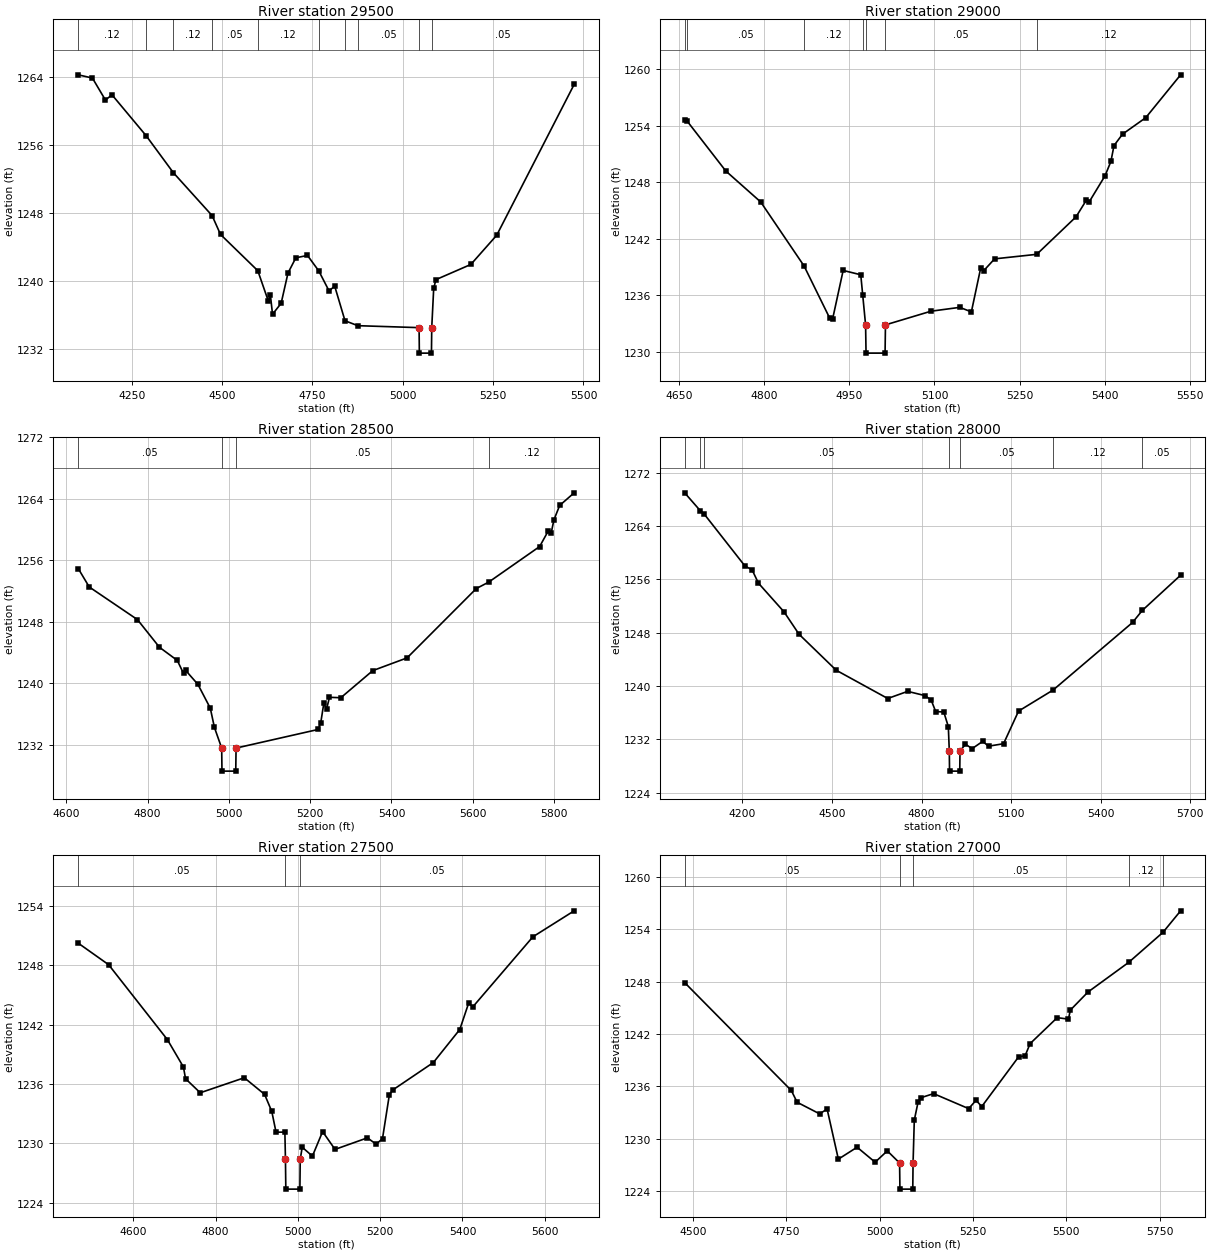
Type RM Length L Ch R = 1,29500,500,500,500
BEGIN DESCRIPTION:
BULLHEAD CREEK 59.0
END DESCRIPTION:
XS GIS Cut Line= 3
      2761055.66     10200453.12      2761890.75     10200123.46
      2762305.73     10200353.13
#Sta/Elev= 30
  4102.2 1264.23  4141.5 1263.85  4177.5 1261.26  4195.6 1261.88  4290.0 1257.07
  4365.4 1252.71  4472.6 1247.66  4495.9 1245.44  4599.1 1241.17  4628.5 1237.56
  4633.8 1238.33  4639.8 1236.05  4663.6 1237.33  4682.6 1240.90  4704.3 1242.69
  4736.5 1242.97  4767.9 1241.14  4796.2 1238.79  4811.8 1239.36  4840.3 1235.28
  4875.9 1234.70  5045.3 1234.47  5046.0 1231.47  5079.5 1231.47  5080.3 1234.47
  5085.7 1239.08  5091.8 1240.12  5188.5 1241.91  5260.1 1245.35  5474.3 1263.10
#Mann=10,-1,0
  4102.2    0.12       0  4290.0    0.05       0  4365.4    0.12       0
  4472.6    0.05       0  4599.1    0.12       0  4767.9    0.05       0
  4840.3    0.12       0  4875.9    0.05       0  5045.3    0.03       0
  5080.3    0.05       0
Bank Sta=5045.3,5080.3
Exp/Cntr=0.3,0.1

Type RM Length L Ch R = 1,29000,500,500,500
BEGIN DESCRIPTION:
BULLHEAD CREEK 58.0
END DESCRIPTION:
XS GIS Cut Line= 3
      2761355.64     10200653.12      2761684.50     10200567.19
      2762205.66     10200453.12
#Sta/Elev= 30
  4660.1 1254.60  4664.0 1254.51  4732.5 1249.18  4794.0 1245.89  4870.4 1239.09
  4915.3 1233.58  4920.5 1233.43  4939.2 1238.62  4970.2 1238.16  4973.7 1235.97
  4978.7 1232.84  4979.5 1229.84  5013.0 1229.84  5013.7 1232.84  5093.8 1234.29
  5144.5 1234.70  5165.0 1234.22  5181.6 1238.93  5186.7 1238.59  5205.9 1239.85
  5280.1 1240.33  5349.3 1244.31  5367.2 1246.05  5372.3 1245.88  5400.4 1248.67
  5410.7 1250.19  5416.2 1251.88  5431.2 1253.09  5472.1 1254.84  5533.5 1259.39
#Mann=7,-1,0
  4660.1    0.12       0  4664.0    0.05       0  4870.4    0.12       0
  4973.7    0.05       0  4978.7    0.03       0  5013.7    0.05       0
  5280.1    0.12       0
Bank Sta=4978.7,5013.7
Exp/Cntr=0.3,0.1

Type RM Length L Ch R = 1,28500,500,500,500
BEGIN DESCRIPTION:
BULLHEAD CREEK 57.0
END DESCRIPTION:
XS GIS Cut Line= 3
      2761355.64     10200953.10      2761720.72     10201017.41
      2762355.70     10200453.10
#Sta/Elev= 30
  4629.3 1254.92  4656.4 1252.52  4775.0 1248.27  4829.2 1244.67  4873.0 1242.96
  4888.5 1241.26  4893.6 1241.66  4923.8 1239.84  4954.3 1236.74  4964.4 1234.24
  4982.3 1231.55  4983.0 1228.55  5016.9 1228.55  5017.7 1231.55  5219.4 1233.97
  5226.1 1234.86  5233.6 1237.39  5240.3 1236.62  5247.5 1238.16  5275.4 1238.10
  5354.0 1241.63  5438.5 1243.29  5608.7 1252.31  5639.3 1253.15  5764.6 1257.78
  5785.5 1259.78  5793.0 1259.54  5799.7 1261.25  5813.9 1263.13  5849.5 1264.77
#Mann=4,-1,0
  4629.3    0.05       0  4982.3    0.03       0  5017.7    0.05       0
  5639.3    0.12       0
Bank Sta=4982.3,5017.7
Exp/Cntr=0.3,0.1

Type RM Length L Ch R = 1,28000,500,500,500
BEGIN DESCRIPTION:
BULLHEAD CREEK 56.0
END DESCRIPTION:
XS GIS Cut Line= 3
      2761005.69     10200953.11      2761841.58     10201488.97
      2762505.69     10201553.11
#Sta/Elev= 30
  4007.1 1268.96  4059.3 1266.28  4072.0 1265.80  4209.0 1257.98  4232.8 1257.41
  4253.9 1255.42  4339.7 1251.11  4390.0 1247.75  4514.3 1242.36  4686.8 1238.12
  4753.5 1239.19  4811.0 1238.56  4832.1 1237.89  4847.4 1236.16  4874.4 1236.10
  4889.6 1233.91  4892.9 1230.23  4893.7 1227.23  4927.9 1227.23  4928.7 1230.23
  4947.1 1231.27  4969.2 1230.60  5004.6 1231.69  5024.2 1230.97  5074.5 1231.34
  5124.7 1236.23  5240.7 1239.40  5506.3 1249.52  5538.8 1251.32  5667.2 1256.61
#Mann=7,-1,0
  4007.1    0.05       0  4059.3    0.12       0  4072.0    0.05       0
  4892.9    0.03       0  4928.7    0.05       0  5240.7    0.12       0
  5538.8    0.05       0
Bank Sta=4892.9,4928.7
Exp/Cntr=0.3,0.1

Type RM Length L Ch R = 1,27500,500,500,500
BEGIN DESCRIPTION:
BULLHEAD CREEK 55.0
END DESCRIPTION:
XS GIS Cut Line= 3
      2761205.71     10202053.11      2761727.72     10201940.56
      2762355.72     10201703.10
#Sta/Elev= 30
  4466.0 1250.25  4539.9 1248.07  4682.7 1240.49  4721.7 1237.72  4726.9 1236.53
  4762.6 1235.11  4869.7 1236.63  4919.0 1234.95  4936.5 1233.22  4946.8 1231.12
  4968.3 1231.13  4969.7 1228.36  4970.6 1225.36  5004.8 1225.36  5005.6 1228.36
  5010.4 1229.60  5035.2 1228.70  5060.0 1231.18  5090.2 1229.38  5168.9 1230.55
  5190.3 1229.90  5205.6 1230.48  5222.3 1234.92  5230.4 1235.39  5329.2 1238.17
  5393.4 1241.51  5414.8 1244.16  5425.5 1243.82  5571.1 1250.89  5671.4 1253.52
#Mann=3,-1,0
  4466.0    0.05       0  4969.7    0.03       0  5005.6    0.05       0
Bank Sta=4969.7,5005.6
Exp/Cntr=0.3,0.1

Type RM Length L Ch R = 1,27000,500,500,500
BEGIN DESCRIPTION:
BULLHEAD CREEK 54.0
END DESCRIPTION:
XS GIS Cut Line= 3
      2761205.67     10202353.11      2761726.06     10202398.92
      2762505.66     10202603.11
#Sta/Elev= 30
  4477.6 1247.89  4763.2 1235.51  4778.8 1234.16  4839.0 1232.83  4859.1 1233.38
  4889.2 1227.63  4939.4 1229.00  4987.7 1227.28  5020.3 1228.58  5053.2 1227.19
  5054.1 1224.19  5088.5 1224.19  5089.3 1227.19  5092.6 1232.11  5103.0 1234.24
  5111.7 1234.70  5144.3 1235.15  5238.1 1233.43  5258.0 1234.38  5273.3 1233.67
  5371.8 1239.36  5389.4 1239.50  5402.8 1240.89  5475.4 1243.87  5505.4 1243.70
  5510.6 1244.74  5557.8 1246.81  5666.7 1250.21  5758.6 1253.66  5805.9 1256.13
#Mann=5,-1,0
  4477.6    0.05       0  5053.2    0.03       0  5089.3    0.05       0
  5666.7    0.12       0  5758.6    0.05       0
Bank Sta=5053.2,5089.3
Exp/Cntr=0.3,0.1

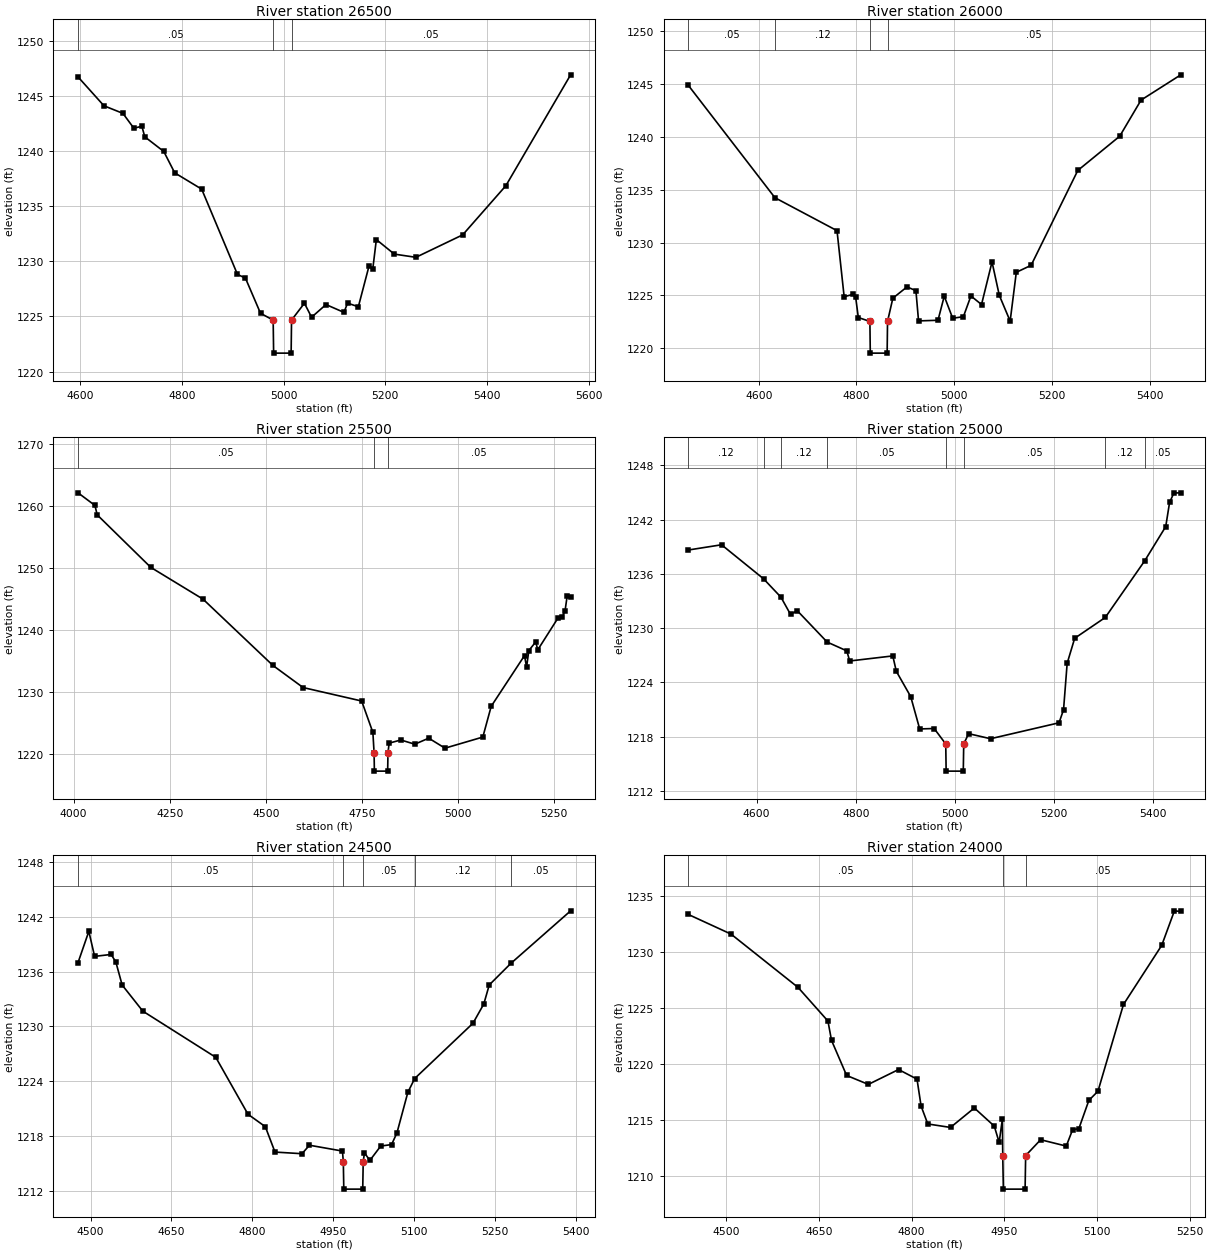
Type RM Length L Ch R = 1,26500,500,500,500
BEGIN DESCRIPTION:
BULLHEAD CREEK 53.0
END DESCRIPTION:
XS GIS Cut Line= 3
      2761155.65     10202603.09      2761504.91     10202806.15
      2761905.69     10203203.11
#Sta/Elev= 30
  4596.0 1246.75  4646.9 1244.13  4684.2 1243.44  4705.7 1242.09  4721.4 1242.27
  4727.2 1241.31  4764.5 1239.98  4786.0 1238.04  4839.0 1236.56  4909.3 1228.82
  4925.0 1228.48  4954.6 1225.29  4979.5 1224.67  4980.4 1221.67  5014.8 1221.67
  5015.6 1224.67  5040.9 1226.20  5055.0 1224.93  5083.3 1226.08  5118.6 1225.37
  5125.7 1226.21  5146.9 1225.88  5168.1 1229.62  5175.2 1229.29  5182.3 1231.98
  5217.6 1230.66  5260.0 1230.37  5352.0 1232.41  5436.8 1236.87  5564.1 1246.94
#Mann=3,-1,0
  4596.0    0.05       0  4979.5    0.05       0  5015.6    0.05       0
Bank Sta=4979.5,5015.6
Exp/Cntr=0.3,0.1

Type RM Length L Ch R = 1,26000,500,500,500
BEGIN DESCRIPTION:
BULLHEAD CREEK 52.0
END DESCRIPTION:
XS GIS Cut Line= 3
      2761105.69     10202753.12      2761320.05     10203253.55
      2761555.70     10203653.13
#Sta/Elev= 30
  4455.6 1244.89  4633.1 1234.24  4760.2 1231.12  4774.8 1224.87  4792.8 1225.09
  4798.4 1224.81  4803.8 1222.90  4827.5 1222.53  4828.3 1219.53  4862.8 1219.53
  4863.6 1222.53  4874.5 1224.73  4903.5 1225.80  4921.7 1225.44  4927.1 1222.58
  4966.9 1222.64  4979.7 1224.92  4997.0 1222.83  5018.9 1222.98  5034.3 1224.94
  5056.0 1224.13  5077.5 1228.16  5092.4 1225.00  5114.6 1222.56  5127.2 1227.18
  5157.5 1227.84  5253.1 1236.82  5338.9 1240.06  5382.6 1243.48  5463.9 1245.87
#Mann=4,-1,0
  4455.6    0.05       0  4633.1    0.12       0  4827.5    0.05       0
  4863.6    0.05       0
Bank Sta=4827.5,4863.6
Exp/Cntr=0.3,0.1

Type RM Length L Ch R = 1,25500,500,500,500
BEGIN DESCRIPTION:
BULLHEAD CREEK 51.0
END DESCRIPTION:
XS GIS Cut Line= 3
      2760205.70     10203103.12      2761036.69     10203638.48
      2761305.68     10203753.11
#Sta/Elev= 30
  4011.5 1262.11  4055.4 1260.08  4061.3 1258.56  4200.6 1250.10  4336.6 1244.97
  4518.1 1234.30  4596.7 1230.73  4749.0 1228.56  4778.2 1223.50  4781.3 1220.26
  4782.1 1217.26  4816.6 1217.26  4817.5 1220.26  4820.5 1221.77  4850.9 1222.28
  4887.2 1221.60  4923.5 1222.57  4965.7 1220.96  5064.1 1222.75  5085.9 1227.71
  5172.5 1235.88  5177.9 1234.03  5183.7 1236.69  5201.6 1238.08  5207.0 1236.81
  5259.8 1241.96  5270.7 1242.12  5277.9 1243.09  5283.3 1245.43  5292.4 1245.40
#Mann=3,-1,0
  4011.5    0.05       0  4781.3    0.03       0  4817.5    0.05       0
Bank Sta=4781.3,4817.5
Exp/Cntr=0.3,0.1

Type RM Length L Ch R = 1,25000,500,500,500
BEGIN DESCRIPTION:
BULLHEAD CREEK 50.0
END DESCRIPTION:
XS GIS Cut Line= 3
      2760355.64     10203803.09      2760850.86     10204013.60
      2761255.70     10203803.10
#Sta/Elev= 30
  4461.9 1238.63  4529.2 1239.21  4614.0 1235.45  4649.1 1233.42  4668.4 1231.52
  4682.0 1231.93  4742.4 1228.46  4782.0 1227.49  4787.9 1226.37  4874.9 1226.93
  4882.0 1225.23  4911.1 1222.43  4929.2 1218.86  4958.4 1218.91  4981.8 1217.20
  4982.6 1214.20  5017.2 1214.20  5018.1 1217.20  5028.0 1218.34  5072.2 1217.78
  5210.5 1219.54  5219.6 1220.98  5226.9 1226.11  5242.1 1228.88  5303.9 1231.18
  5383.5 1237.44  5425.9 1241.22  5433.7 1243.90  5442.4 1244.93  5456.3 1244.95
#Mann=8,-1,0
  4461.9    0.12       0  4614.0    0.05       0  4649.1    0.12       0
  4742.4    0.05       0  4981.8    0.05       0  5018.1    0.05       0
  5303.9    0.12       0  5383.5    0.05       0
Bank Sta=4981.8,5018.1
Exp/Cntr=0.3,0.1

Type RM Length L Ch R = 1,24500,500,500,500
BEGIN DESCRIPTION:
BULLHEAD CREEK 49.0
END DESCRIPTION:
XS GIS Cut Line= 3
      2760605.65     10204503.12      2761117.76     10204396.45
      2761505.64     10204353.12
#Sta/Elev= 30
  4476.9 1236.98  4496.9 1240.40  4507.6 1237.66  4538.2 1237.87  4546.9 1237.06
  4558.7 1234.52  4597.0 1231.66  4732.3 1226.60  4792.1 1220.36  4824.2 1219.00
  4842.1 1216.22  4892.2 1216.04  4906.0 1216.97  4967.2 1216.33  4968.8 1215.16
  4969.7 1212.16  5004.8 1212.16  5005.7 1215.16  5008.0 1216.14  5018.0 1215.30
  5038.2 1216.88  5058.3 1217.04  5068.3 1218.33  5088.5 1222.77  5101.2 1224.28
  5209.2 1230.33  5229.3 1232.44  5239.4 1234.53  5279.3 1236.88  5390.3 1242.65
#Mann=5,-1,0
  4476.9    0.05       0  4968.8    0.05       0  5005.7    0.05       0
  5101.2    0.12       0  5279.3    0.05       0
Bank Sta=4968.8,5005.7
Exp/Cntr=0.3,0.1

Type RM Length L Ch R = 1,24000,500,500,500
BEGIN DESCRIPTION:
BULLHEAD CREEK 48.0
END DESCRIPTION:
XS GIS Cut Line= 3
      2760705.67     10204653.10      2761227.52     10204858.72
      2761455.65     10204803.12
#Sta/Elev= 30
  4439.1 1233.39  4508.2 1231.63  4616.5 1226.86  4664.8 1223.85  4670.6 1222.12
  4695.0 1218.98  4730.1 1218.18  4778.9 1219.51  4808.7 1218.65  4815.3 1216.24
  4826.1 1214.64  4862.8 1214.33  4901.3 1216.07  4933.5 1214.45  4941.4 1212.99
  4946.7 1215.12  4947.2 1211.81  4948.2 1208.81  4983.3 1208.81  4984.2 1211.81
  5008.4 1213.23  5049.8 1212.66  5059.9 1214.11  5070.2 1214.23  5086.3 1216.75
  5101.0 1217.57  5142.2 1225.33  5204.0 1230.62  5224.5 1233.71  5234.8 1233.65
#Mann=3,-1,0
  4439.1    0.05       0  4947.2    0.03       0  4984.2    0.05       0
Bank Sta=4947.2,4984.2
Exp/Cntr=0.3,0.1

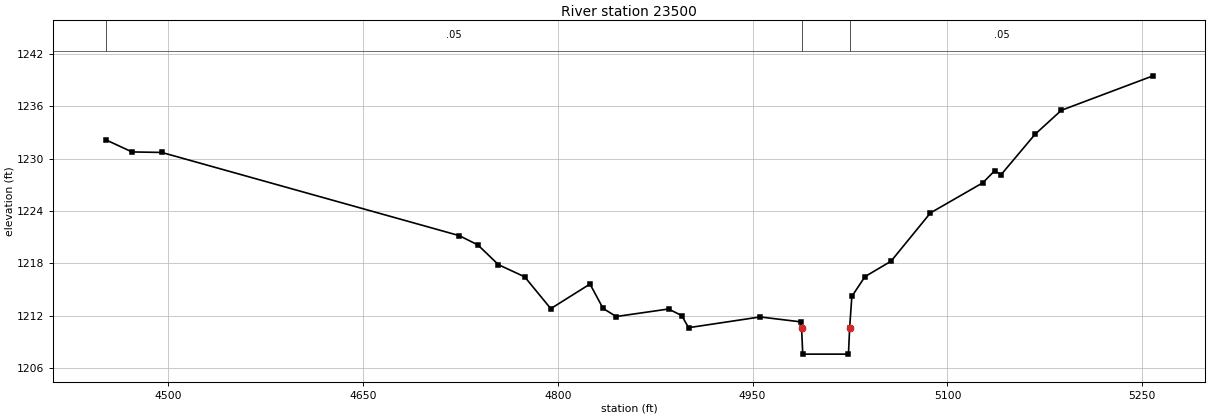
Type RM Length L Ch R = 1,23500,500,500,500
BEGIN DESCRIPTION:
BULLHEAD CREEK 47.0
END DESCRIPTION:
XS GIS Cut Line= 3
      2760805.65     10205403.12      2761349.52     10205335.98
      2761605.72     10205303.11
#Sta/Elev= 30
  4452.0 1232.16  4472.2 1230.77  4495.1 1230.71  4724.1 1221.18  4738.5 1220.11
  4754.3 1217.85  4774.5 1216.46  4794.6 1212.81  4824.8 1215.63  4834.9 1212.83
  4845.0 1211.91  4885.3 1212.77  4895.4 1212.02  4900.7 1210.63  4955.8 1211.86
  4986.9 1211.30  4987.7 1210.60  4988.6 1207.60  5023.8 1207.60  5024.7 1210.60
  5026.4 1214.21  5036.5 1216.48  5056.6 1218.25  5086.9 1223.78  5127.2 1227.23
  5136.3 1228.60  5141.4 1228.18  5167.5 1232.80  5187.7 1235.54  5258.3 1239.49
#Mann=3,-1,0
  4452.0    0.05       0  4987.7    0.03       0  5024.7    0.05       0
Bank Sta=4987.7,5024.7
Exp/Cntr=0.3,0.1