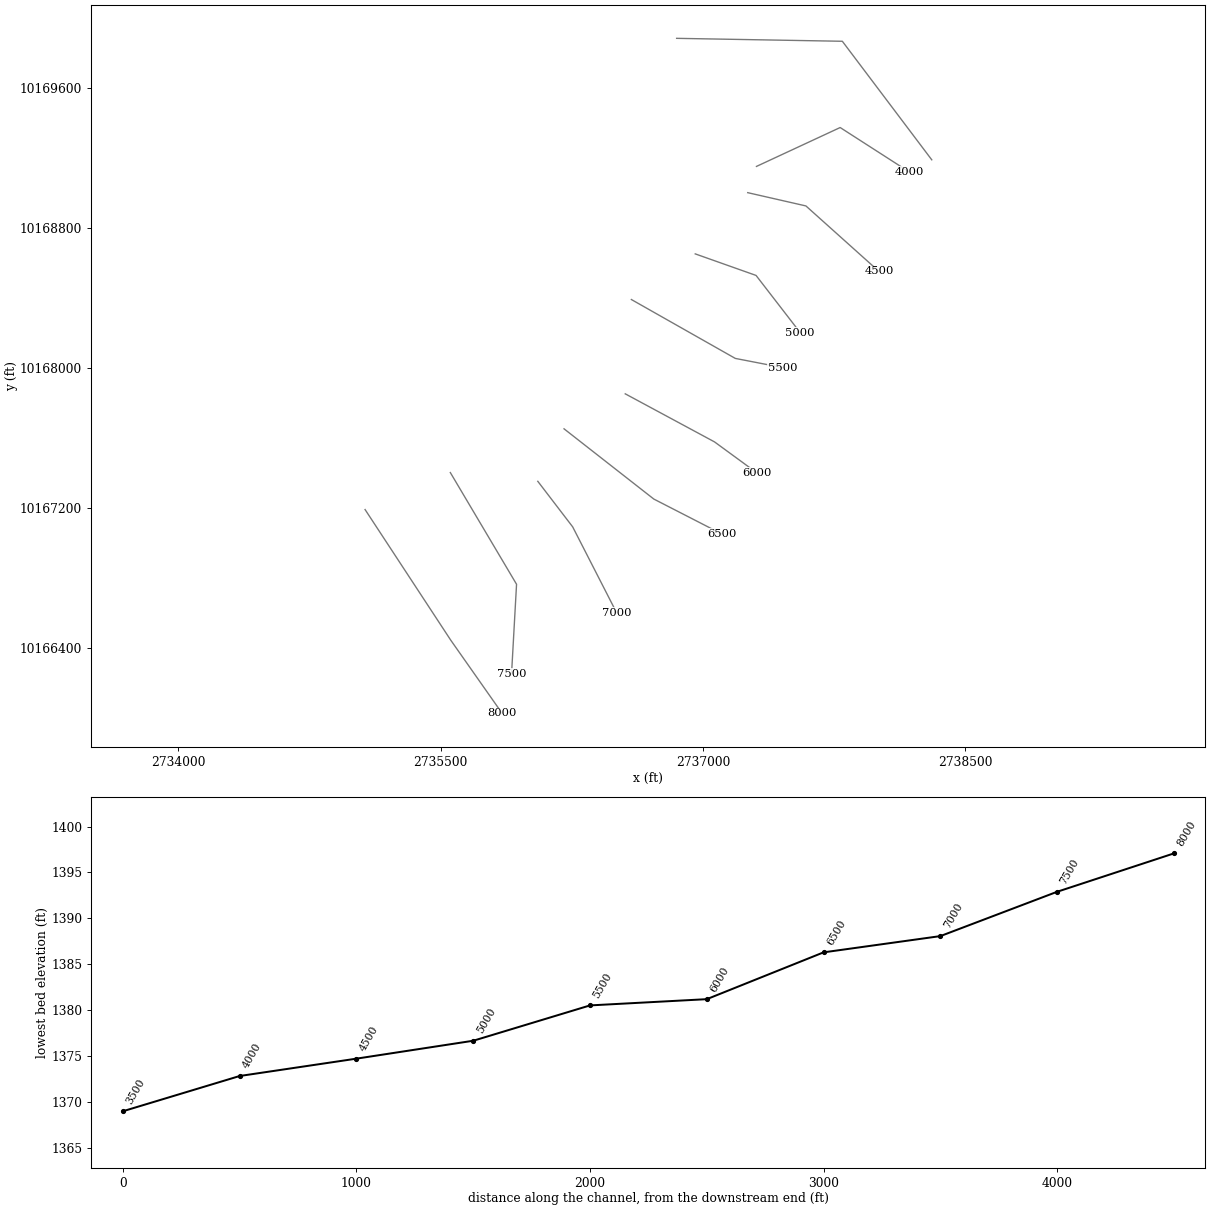
HEC-RAS study CHERRY SPRING CREEK.prj: CHERRY SPRING CREEK Base Level Engineering

--- CHERRY SPRING CREEK.g01 (geometry) --- (continued)

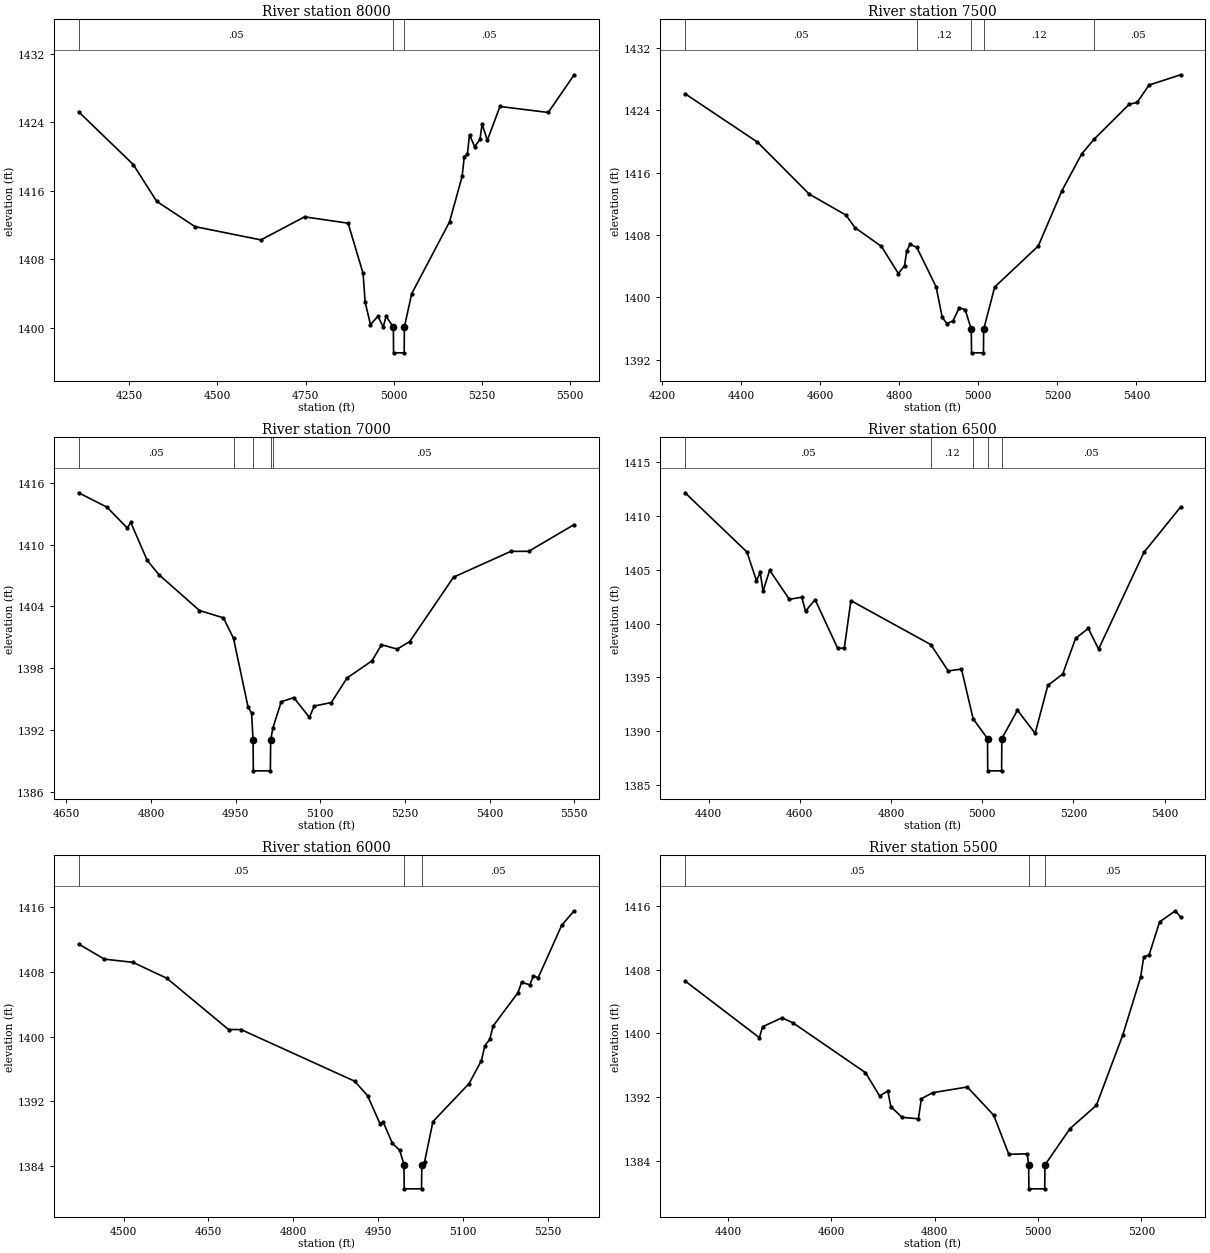
Type RM Length L Ch R = 1,8000,500,500,500
BEGIN DESCRIPTION:
CHERRY SPRING CREEK 16.0
END DESCRIPTION:
XS GIS Cut Line= 3
      2735068.37     10167191.60      2735558.27     10166444.74
      2735851.95     10166026.56
#Sta/Elev= 30
  4106.8 1425.21  4261.7 1419.05  4328.0 1414.76  4436.5 1411.81  4623.4 1410.26
  4747.0 1412.95  4870.4 1412.21  4912.7 1406.37  4918.7 1403.00  4933.8 1400.37
  4954.9 1401.35  4970.0 1400.09  4978.0 1401.35  4998.7 1400.08  4999.2 1397.08
  5029.3 1397.08  5029.8 1400.08  5050.6 1403.98  5157.8 1412.36  5193.5 1417.67
  5199.6 1419.99  5208.3 1420.24  5214.4 1422.51  5229.2 1421.14  5244.0 1421.98
  5250.1 1423.76  5265.0 1421.89  5300.7 1425.83  5437.5 1425.13  5511.0 1429.53
#Mann=3,-1,0
  4106.8    0.05       0  4998.7    0.05       0  5029.8    0.05       0
Bank Sta=4998.7,5029.8
Exp/Cntr=0.3,0.1

Type RM Length L Ch R = 1,7500,500,500,500
BEGIN DESCRIPTION:
CHERRY SPRING CREEK 15.0
END DESCRIPTION:
XS GIS Cut Line= 3
      2735555.70     10167403.09      2735934.23     10166764.56
      2735905.69     10166253.16
#Sta/Elev= 30
  4257.7 1426.11  4440.9 1419.91  4571.6 1413.26  4665.0 1410.55  4687.8 1408.94
  4754.7 1406.55  4797.6 1403.06  4813.2 1404.07  4819.0 1406.01  4827.3 1406.79
  4844.1 1406.43  4893.1 1401.37  4908.7 1397.44  4920.4 1396.66  4936.0 1396.98
  4951.6 1398.68  4966.8 1398.43  4982.3 1395.90  4982.8 1392.90  5013.0 1392.90
  5013.5 1395.90  5041.5 1401.34  5151.7 1406.59  5211.8 1413.69  5261.9 1418.41
  5293.5 1420.30  5382.0 1424.76  5402.1 1424.99  5432.1 1427.22  5512.2 1428.54
#Mann=5,-1,0
  4257.7    0.05       0  4844.1    0.12       0  4982.3    0.07       0
  5013.5    0.12       0  5293.5    0.05       0
Bank Sta=4982.3,5013.5
Exp/Cntr=0.3,0.1

Type RM Length L Ch R = 1,7000,500,500,500
BEGIN DESCRIPTION:
CHERRY SPRING CREEK 14.0
END DESCRIPTION:
XS GIS Cut Line= 3
      2736055.71     10167353.08      2736255.10     10167092.64
      2736505.67     10166603.14
#Sta/Elev= 30
  4672.0 1415.02  4722.3 1413.62  4758.1 1411.61  4764.4 1412.14  4793.5 1408.47
  4814.3 1407.08  4886.1 1403.61  4928.5 1402.90  4946.4 1400.91  4972.1 1394.27
  4978.4 1393.68  4981.0 1391.07  4981.5 1388.07  5011.7 1388.07  5012.2 1391.07
  5016.4 1392.27  5030.9 1394.76  5053.1 1395.17  5080.9 1393.25  5089.3 1394.35
  5119.7 1394.69  5147.5 1397.07  5191.9 1398.74  5208.5 1400.29  5236.4 1399.87
  5258.6 1400.60  5336.2 1406.84  5437.6 1409.34  5469.4 1409.35  5549.9 1411.94
#Mann=5,-1,0
  4672.0    0.05       0  4946.4    0.12       0  4981.0    0.07       0
  5012.2    0.12       0  5016.4    0.05       0
Bank Sta=4981,5012.2
Exp/Cntr=0.3,0.1

Type RM Length L Ch R = 1,6500,500,500,500
BEGIN DESCRIPTION:
CHERRY SPRING CREEK 13.0
END DESCRIPTION:
XS GIS Cut Line= 3
      2736205.68     10167653.12      2736718.83     10167251.70
      2737105.73     10167053.09
#Sta/Elev= 30
  4348.5 1412.16  4484.1 1406.65  4505.0 1403.98  4513.1 1404.75  4519.4 1403.01
  4533.9 1404.96  4577.0 1402.25  4604.4 1402.45  4612.5 1401.14  4633.4 1402.23
  4683.1 1397.69  4697.6 1397.73  4712.0 1402.13  4887.2 1398.04  4925.4 1395.59
  4954.4 1395.77  4980.0 1391.14  5011.5 1389.30  5012.0 1386.30  5042.4 1386.30
  5042.9 1389.30  5077.2 1391.94  5115.9 1389.79  5143.7 1394.24  5176.3 1395.30
  5204.7 1398.63  5232.5 1399.54  5255.0 1397.62  5354.4 1406.62  5434.9 1410.84
#Mann=5,-1,0
  4348.5    0.05       0  4887.2    0.12       0  4980.0    0.05       0
  5011.5    0.05       0  5042.9    0.05       0
Bank Sta=5011.5,5042.9
Exp/Cntr=0.3,0.1

Type RM Length L Ch R = 1,6000,500,500,500
BEGIN DESCRIPTION:
CHERRY SPRING CREEK 12.0
END DESCRIPTION:
XS GIS Cut Line= 3
      2736555.66     10167853.12      2737065.98     10167578.34
      2737305.67     10167403.12
#Sta/Elev= 30
  4420.4 1411.42  4465.9 1409.55  4516.2 1409.16  4576.2 1407.20  4685.7 1400.86
  4707.6 1400.86  4908.8 1394.48  4931.5 1392.69  4953.4 1389.25  4959.1 1389.45
  4975.3 1386.83  4988.3 1385.96  4995.8 1384.20  4996.3 1381.20  5026.9 1381.20
  5027.4 1384.20  5032.4 1384.56  5047.1 1389.50  5111.1 1394.20  5132.8 1397.03
  5139.0 1398.87  5147.5 1399.65  5153.7 1401.31  5197.7 1405.43  5203.9 1406.69
  5218.5 1406.38  5224.7 1407.50  5233.2 1407.25  5274.9 1413.74  5296.9 1415.52
#Mann=3,-1,0
  4420.4    0.05       0  4995.8    0.05       0  5027.4    0.05       0
Bank Sta=4995.8,5027.4
Exp/Cntr=0.3,0.1

Type RM Length L Ch R = 1,5500,500,500,500
BEGIN DESCRIPTION:
CHERRY SPRING CREEK 11.0
END DESCRIPTION:
XS GIS Cut Line= 3
      2736590.66     10168392.21      2737184.73     10168055.60
      2737455.69     10168003.11
#Sta/Elev= 30
  4317.2 1406.58  4460.9 1399.47  4467.1 1400.84  4504.6 1401.96  4526.2 1401.32
  4666.2 1395.09  4693.6 1392.16  4709.5 1392.79  4715.2 1390.83  4736.8 1389.49
  4768.6 1389.30  4774.4 1391.82  4796.0 1392.57  4863.2 1393.29  4914.3 1389.75
  4943.6 1384.85  4979.2 1384.91  4981.9 1383.52  4982.4 1380.52  5013.0 1380.52
  5013.5 1383.52  5062.1 1388.08  5113.0 1390.99  5164.0 1399.80  5198.4 1407.02
  5204.7 1409.61  5214.9 1409.83  5235.3 1413.99  5265.8 1415.38  5276.0 1414.58
#Mann=3,-1,0
  4317.2    0.05       0  4981.9    0.05       0  5013.5    0.05       0
Bank Sta=4981.9,5013.5
Exp/Cntr=0.3,0.1

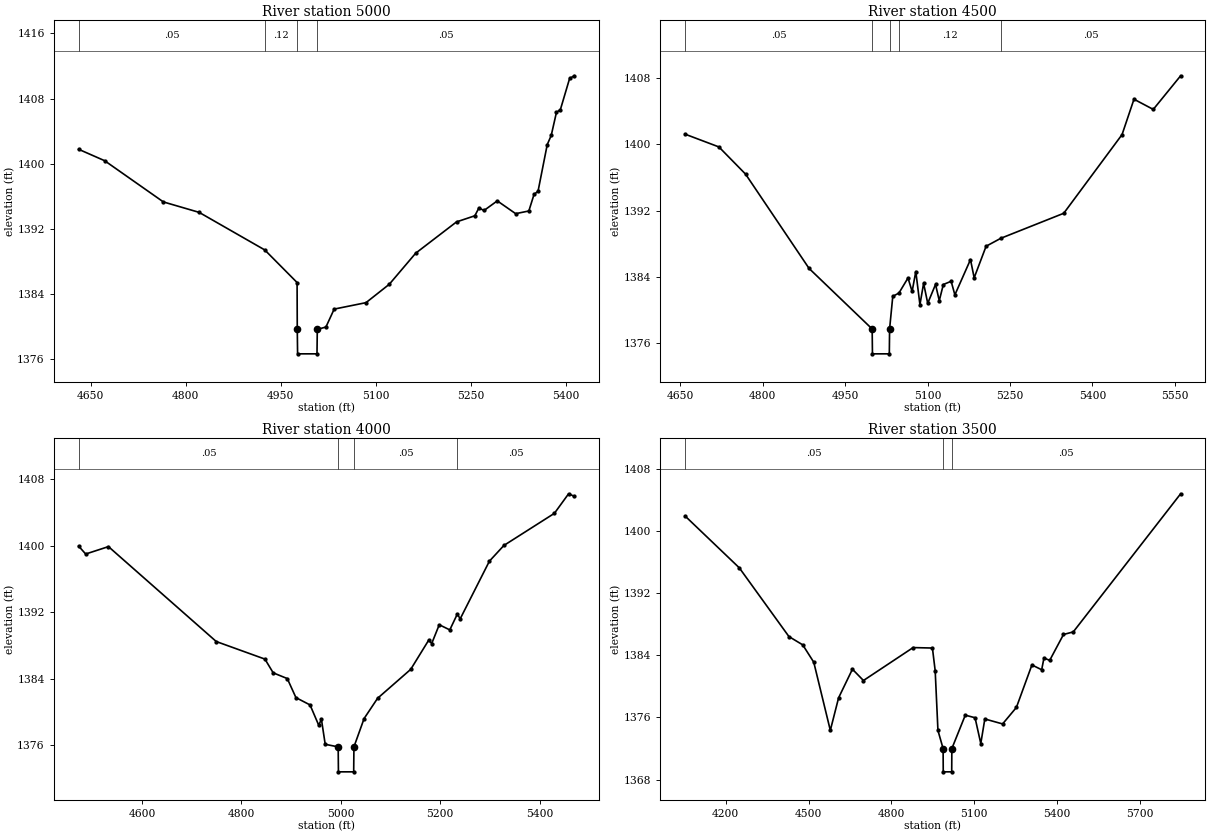
Type RM Length L Ch R = 1,5000,500,500,500
BEGIN DESCRIPTION:
CHERRY SPRING CREEK 10.0
END DESCRIPTION:
XS GIS Cut Line= 3
      2736955.69     10168653.11      2737303.32     10168529.96
      2737555.66     10168203.14
#Sta/Elev= 30
  4631.2 1401.77  4672.2 1400.37  4764.9 1395.31  4821.3 1394.03  4924.8 1389.42
  4975.8 1385.42  4976.1 1379.67  4976.6 1376.67  5007.2 1376.67  5007.7 1379.67
  5021.3 1379.96  5034.3 1382.16  5084.5 1382.95  5121.3 1385.21  5162.9 1389.02
  5227.3 1392.86  5256.2 1393.61  5262.6 1394.57  5270.7 1394.26  5291.6 1395.44
  5320.6 1393.87  5341.4 1394.20  5349.6 1396.24  5355.9 1396.62  5370.4 1402.34
  5376.7 1403.47  5384.9 1406.29  5391.2 1406.65  5405.7 1410.46  5412.9 1410.79
#Mann=4,-1,0
  4631.2    0.05       0  4924.8    0.12       0  4976.1    0.05       0
  5007.7    0.05       0
Bank Sta=4976.1,5007.7
Exp/Cntr=0.3,0.1

Type RM Length L Ch R = 1,4500,500,500,500
BEGIN DESCRIPTION:
CHERRY SPRING CREEK 9.0
END DESCRIPTION:
XS GIS Cut Line= 3
      2737255.71     10169003.11      2737588.36     10168927.22
      2738005.71     10168553.08
#Sta/Elev= 30
  4658.8 1401.24  4720.3 1399.70  4768.8 1396.42  4884.4 1385.03  4999.2 1377.72
  4999.7 1374.72  5030.4 1374.72  5030.9 1377.72  5036.7 1381.66  5047.9 1382.06
  5064.4 1383.88  5071.9 1382.25  5078.6 1384.66  5086.1 1380.65  5092.8 1383.23
  5100.3 1380.82  5114.5 1383.10  5121.3 1381.14  5128.7 1383.09  5142.9 1383.48
  5149.7 1381.84  5178.1 1386.10  5184.8 1383.90  5206.5 1387.71  5233.3 1388.67
  5347.8 1391.69  5453.9 1401.19  5475.6 1405.46  5510.7 1404.23  5560.5 1408.29
#Mann=5,-1,0
  4658.8    0.05       0  4999.2    0.05       0  5030.9    0.05       0
  5047.9    0.12       0  5233.3    0.05       0
Bank Sta=4999.2,5030.9
Exp/Cntr=0.3,0.1

Type RM Length L Ch R = 1,4000,500,500,500
BEGIN DESCRIPTION:
CHERRY SPRING CREEK 8.0
END DESCRIPTION:
XS GIS Cut Line= 3
      2737305.69     10169153.12      2737784.07     10169375.40
      2738179.17     10169121.40
#Sta/Elev= 30
  4472.5 1399.96  4486.7 1399.01  4532.5 1399.90  4749.5 1388.49  4847.4 1386.38
  4864.0 1384.73  4892.4 1384.04  4909.8 1381.75  4938.2 1380.87  4955.6 1378.44
  4961.1 1379.14  4968.7 1376.14  4994.8 1375.83  4995.3 1372.83  5026.0 1372.83
  5026.5 1375.83  5047.0 1379.24  5074.1 1381.67  5140.8 1385.15  5177.1 1388.67
  5183.0 1388.25  5198.2 1390.51  5219.4 1389.89  5234.3 1391.76  5240.5 1391.24
  5299.1 1398.15  5328.3 1400.04  5429.9 1403.90  5458.5 1406.25  5469.7 1405.95
#Mann=4,-1,0
  4472.5    0.05       0  4994.8    0.05       0  5026.5    0.05       0
  5234.3    0.05       0
Bank Sta=4994.8,5026.5
Exp/Cntr=0.3,0.1

Type RM Length L Ch R = 1,3500,0,0,0
BEGIN DESCRIPTION:
CHERRY SPRING CREEK 7.0
END DESCRIPTION:
XS GIS Cut Line= 3
      2736849.32     10169885.27      2737796.57     10169868.48
      2738307.68     10169190.81
#Sta/Elev= 30
  4052.6 1401.99  4249.0 1395.31  4429.0 1386.44  4479.0 1385.37  4519.0 1383.13
  4579.0 1374.34  4609.0 1378.54  4659.1 1382.23  4699.1 1380.77  4879.1 1385.02
  4949.1 1384.96  4959.1 1382.03  4969.1 1374.33  4987.8 1371.99  4988.3 1368.99
  5019.0 1368.99  5019.5 1371.99  5068.2 1376.30  5103.6 1375.97  5124.4 1372.64
  5139.0 1375.81  5203.5 1375.17  5253.5 1377.30  5309.7 1382.78  5345.1 1382.16
  5353.4 1383.68  5374.2 1383.37  5424.2 1386.71  5459.6 1387.04  5848.8 1404.86
#Mann=3,-1,0
  4052.6    0.05       0  4987.8    0.05       0  5019.5    0.05       0
Bank Sta=4987.8,5019.5
Exp/Cntr=0.3,0.1

Chan Stop Cuts=-1