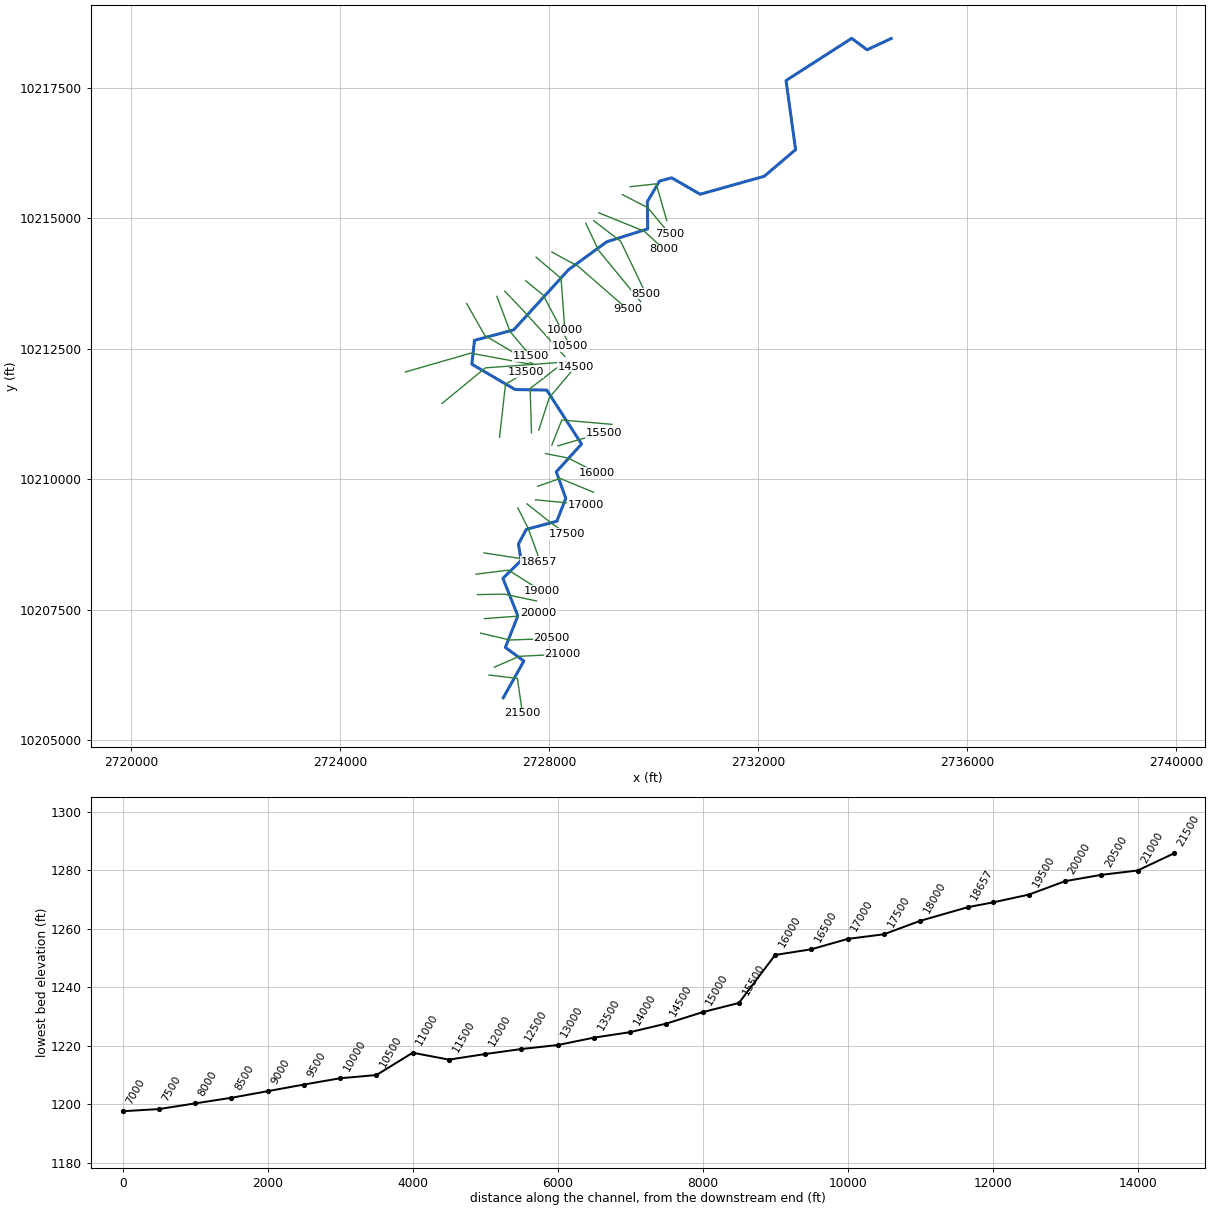
--- HICKORY13.prj (project) ---

Proj Title=HICKORY13 Base Level Engineering
Current Plan=p01
Default Exp/Contr=0.3,0.1
English Units
Geom File=g01
Flow File=f01
Plan File=p01
BEGIN DESCRIPTION:
HICKORY13
END DESCRIPTION:

--- HICKORY13.p01 (plan) ---

Plan Title=Multiple Run
Short Identifier=Multiple
Geom File=g01
Flow File=f01
Subcritical Flow
K Sum by GR= 0
Std Step Tol= 0.01
Critical Tol= 0.01
Num of Std Step Trials= 20
Max Error Tol= 0.3
Flow Tol Ratio= 0.001
Split Flow NTrial= 30
Split Flow Tol= 0.02
Split Flow Ratio= 0.02
Log Output Level= 0
Friction Slope Method= 1
Unsteady Friction Slope Method= 2
Unsteady Bridges Friction Slope Method= 1
Parabolic Critical Depth
Global Vel Dist=  1 , 1 , 1
Global Log Level= 0
CheckData=True
Encroach Param= -1, 0, 0, 0
BEGIN DESCRIPTION:
Multiple Run
END DESCRIPTION:

--- HICKORY13.f01 (steady flow) ---

Flow Title=Multiple
Number of Profiles=7
Profile Names=10-year,25-year,50-year,1pct_min,100-year,1pct_plu,500-year
River Rch & RM= HICKORY13,Reach-1,21500
     142     302     494     266     803    2426    2259
River Rch & RM= HICKORY13,Reach-1,17500
     175     379     626     340    1027    3100    2929
River Rch & RM= HICKORY13,Reach-1,10500
     190     416     689     375    1133    3422    3252
River Rch & RM= HICKORY13,Reach-1,6000
     259     578     971     534    1611    4866    4714
Boundary for River Rch & Prof#=HICKORY13,Reach-1,1
Up Type=0
Dn Type=3
Dn Slope=0.005
Boundary for River Rch & Prof#=HICKORY13,Reach-1,2
Up Type=0
Dn Type=3
Dn Slope=0.005
Boundary for River Rch & Prof#=HICKORY13,Reach-1,3
Up Type=0
Dn Type=3
Dn Slope=0.005
Boundary for River Rch & Prof#=HICKORY13,Reach-1,4
Up Type=0
Dn Type=3
Dn Slope=0.005
Boundary for River Rch & Prof#=HICKORY13,Reach-1,5
Up Type=0
Dn Type=3
Dn Slope=0.005
Boundary for River Rch & Prof#=HICKORY13,Reach-1,6
Up Type=0
Dn Type=3
Dn Slope=0.005
Boundary for River Rch & Prof#=HICKORY13,Reach-1,7
Up Type=0
Dn Type=3
Dn Slope=0.005

--- HICKORY13.g01 (geometry) ---

Geom Title=Existing Conditions

River Reach=HICKORY13,Reach-1
Reach XY= 30
      2727127.00     10205817.00      2727521.25     10206521.00
      2727167.25     10206782.00      2727406.75     10207386.00
      2727120.25     10208104.00      2727469.25     10208448.00
      2727417.25     10208761.00      2727568.25     10209042.00
      2728151.50     10209198.00      2728323.50     10209636.00
      2728142.75     10210144.00      2728625.50     10210677.00
      2727959.00     10211709.00      2727354.75     10211719.00
      2726526.00     10212205.00      2726576.75     10212661.00
      2727327.25     10212862.00      2728382.00     10214019.00
      2729108.50     10214549.00      2729891.25     10214795.00
      2729883.25     10215316.00      2730116.25     10215710.00
      2730349.00     10215773.00      2730895.50     10215459.00
      2732121.25     10215803.00      2732720.75     10216313.00
      2732538.00     10217636.00      2733794.25     10218444.00
      2734088.00     10218225.00      2734549.50     10218440.00

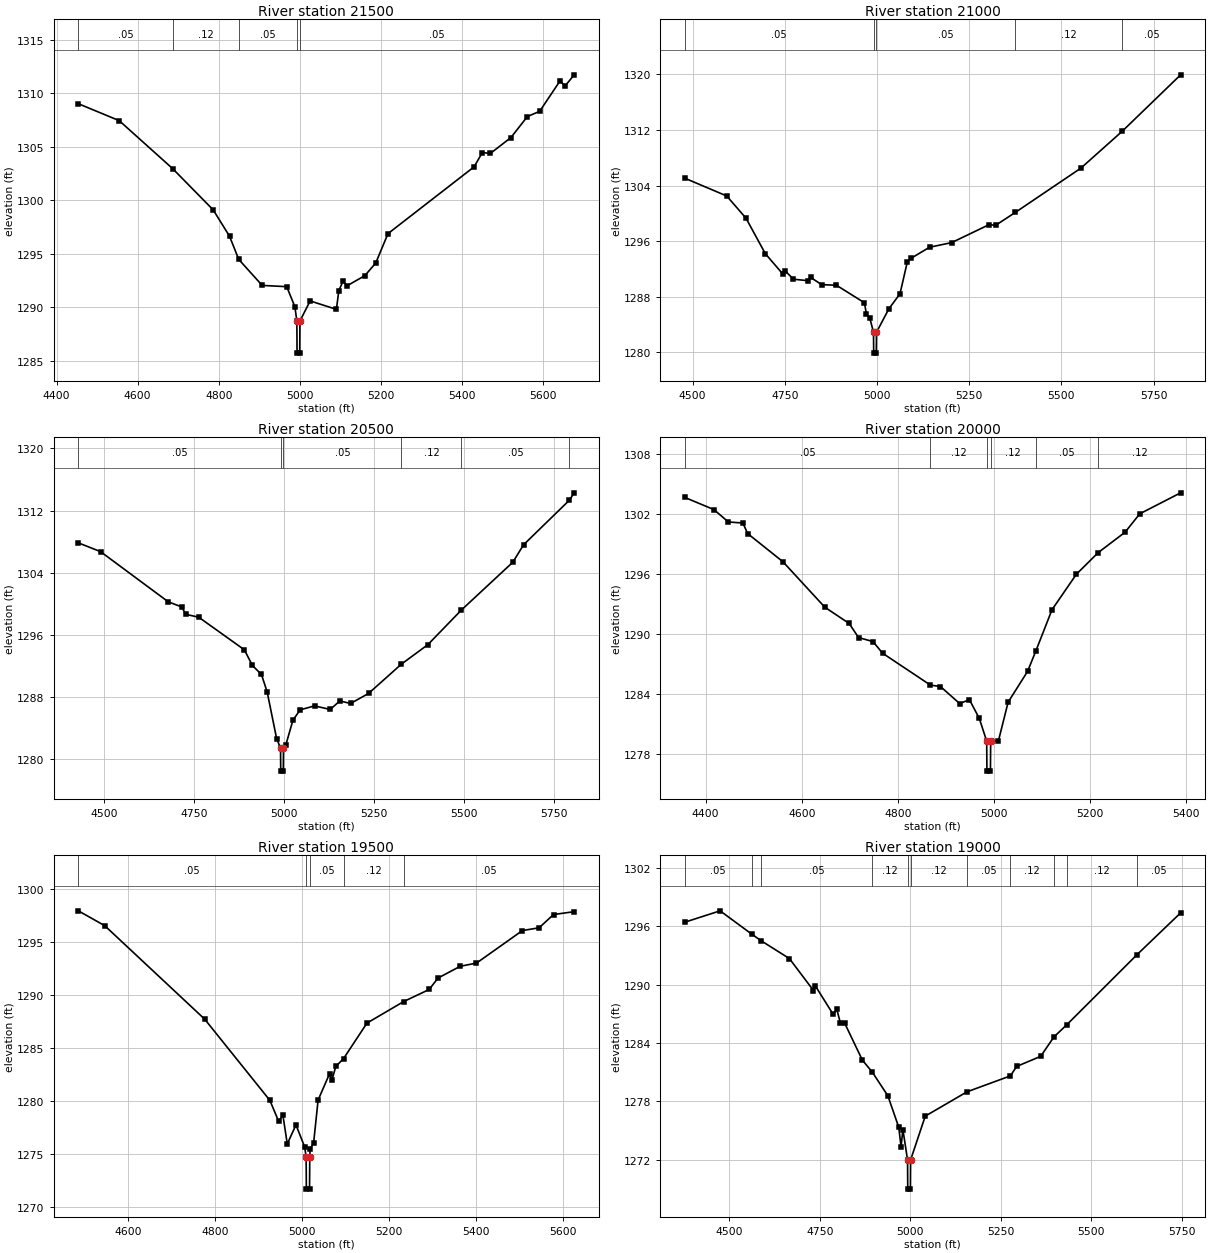
Type RM Length L Ch R = 1,21500,500,500,500
BEGIN DESCRIPTION:
HICKORY13 43.0
END DESCRIPTION:
XS GIS Cut Line= 3
      2726855.66     10206253.11      2727397.99     10206188.14
      2727494.39     10205518.95
#Sta/Elev= 30
  4453.8 1309.03  4554.5 1307.45  4686.7 1302.95  4786.2 1299.11  4826.5 1296.65
  4849.2 1294.48  4907.0 1292.05  4967.5 1291.93  4987.6 1290.06  4992.5 1288.72
  4993.0 1285.72  4999.6 1285.72  5000.1 1288.72  5025.3 1290.60  5090.0 1289.81
  5096.0 1291.57  5106.1 1292.43  5116.2 1292.01  5160.4 1292.97  5186.9 1294.14
  5217.2 1296.89  5429.4 1303.13  5449.6 1304.46  5469.8 1304.39  5520.3 1305.87
  5560.8 1307.83  5591.1 1308.32  5641.6 1311.18  5653.4 1310.67  5676.1 1311.73
#Mann=5,-1,0
  4453.8    0.05       0  4686.7    0.12       0  4849.2    0.05       0
  4992.5    0.05       0  5000.1    0.05       0
Bank Sta=4992.5,5000.1
Exp/Cntr=0.3,0.1

Type RM Length L Ch R = 1,21000,500,500,500
BEGIN DESCRIPTION:
HICKORY13 42.0
END DESCRIPTION:
XS GIS Cut Line= 3
      2726955.64     10206403.09      2727433.39     10206611.18
      2728255.72     10206653.11
#Sta/Elev= 30
  4478.9 1305.06  4592.6 1302.50  4644.9 1299.30  4697.2 1294.20  4744.0 1291.31
  4751.6 1291.69  4773.4 1290.52  4814.3 1290.30  4819.8 1290.79  4849.8 1289.74
  4890.1 1289.65  4965.8 1287.14  4971.3 1285.56  4980.7 1284.90  4990.6 1282.88
  4991.1 1279.88  4998.2 1279.88  4998.7 1282.88  5032.3 1286.26  5062.4 1288.42
  5082.4 1293.04  5092.4 1293.53  5142.5 1295.12  5202.6 1295.79  5302.7 1298.34
  5322.7 1298.31  5375.6 1300.15  5553.0 1306.51  5664.7 1311.80  5823.4 1319.94
#Mann=5,-1,0
  4478.9    0.05       0  4990.6    0.05       0  4998.7    0.05       0
  5375.6    0.12       0  5664.7    0.05       0
Bank Sta=4990.6,4998.7
Exp/Cntr=0.3,0.1

Type RM Length L Ch R = 1,20500,500,500,500
BEGIN DESCRIPTION:
HICKORY13 41.0
END DESCRIPTION:
XS GIS Cut Line= 3
      2726695.78     10207055.39      2727251.33     10206923.44
      2728055.68     10206953.11
#Sta/Elev= 30
  4429.0 1307.83  4490.6 1306.70  4678.8 1300.22  4715.9 1299.57  4727.0 1298.62
  4763.2 1298.24  4889.8 1294.04  4912.0 1292.02  4937.1 1290.87  4953.1 1288.59
  4979.3 1282.58  4990.1 1281.40  4990.6 1278.40  4997.8 1278.40  4998.3 1281.40
  5004.7 1281.76  5024.4 1284.95  5044.4 1286.30  5084.4 1286.81  5128.1 1286.35
  5154.5 1287.45  5184.5 1287.12  5234.5 1288.42  5325.4 1292.19  5398.8 1294.70
  5492.0 1299.17  5634.8 1305.34  5664.5 1307.58  5791.9 1313.34  5804.9 1314.28
#Mann=6,-1,0
  4429.0    0.05       0  4990.1    0.05       0  4998.3    0.05       0
  5325.4    0.12       0  5492.0    0.05       0  5791.9    0.12       0
Bank Sta=4990.1,4998.3
Exp/Cntr=0.3,0.1

Type RM Length L Ch R = 1,20000,500,500,500
BEGIN DESCRIPTION:
HICKORY13 40.0
END DESCRIPTION:
XS GIS Cut Line= 3
      2726765.21     10207333.17      2727406.75     10207380.69
      2727789.52     10207446.02
#Sta/Elev= 30
  4356.7 1303.64  4417.3 1302.42  4447.4 1301.18  4477.5 1301.08  4487.5 1300.02
  4560.9 1297.20  4648.0 1292.65  4698.7 1291.02  4718.2 1289.61  4748.2 1289.21
  4768.3 1288.04  4867.8 1284.85  4888.6 1284.71  4928.7 1283.00  4948.8 1283.40
  4969.5 1281.51  4984.8 1279.24  4985.3 1276.24  4992.6 1276.24  4993.1 1279.24
  5009.1 1279.25  5029.4 1283.14  5069.9 1286.23  5087.1 1288.27  5120.7 1292.40
  5171.4 1295.95  5216.9 1298.12  5272.8 1300.16  5303.3 1302.00  5388.3 1304.10
#Mann=6,-1,0
  4356.7    0.05       0  4867.8    0.12       0  4984.8    0.07       0
  4993.1    0.12       0  5087.1    0.05       0  5216.9    0.12       0
Bank Sta=4984.8,4993.1
Exp/Cntr=0.3,0.1

Type RM Length L Ch R = 1,19500,500,500,500
BEGIN DESCRIPTION:
HICKORY13 39.0
END DESCRIPTION:
XS GIS Cut Line= 3
      2726635.00     10207793.24      2727149.13     10207801.47
      2727762.11     10207672.00
#Sta/Elev= 30
  4485.8 1297.90  4546.5 1296.50  4776.5 1287.68  4926.5 1280.02  4946.5 1278.06
  4956.5 1278.61  4966.5 1275.91  4986.5 1277.71  5006.7 1275.61  5009.9 1274.65
  5010.4 1271.65  5017.7 1271.65  5018.2 1274.65  5019.1 1275.41  5027.1 1276.01
  5037.4 1280.05  5063.8 1282.54  5068.9 1281.90  5078.2 1283.22  5096.1 1283.97
  5149.8 1287.31  5234.2 1289.34  5292.9 1290.48  5313.3 1291.56  5364.4 1292.67
  5401.8 1292.97  5507.5 1296.04  5545.9 1296.30  5579.0 1297.55  5626.5 1297.82
#Mann=5,-1,0
  4485.8    0.05       0  5009.9    0.05       0  5018.2    0.05       0
  5096.1    0.12       0  5234.2    0.05       0
Bank Sta=5009.9,5018.2
Exp/Cntr=0.3,0.1

Type RM Length L Ch R = 1,19000,343,343,343
BEGIN DESCRIPTION:
HICKORY13 38.0
END DESCRIPTION:
XS GIS Cut Line= 3
      2726608.96     10208183.86      2727227.15     10208261.12
      2727859.01     10207862.66
#Sta/Elev= 30
  4377.0 1296.43  4474.5 1297.60  4561.7 1295.21  4587.6 1294.53  4666.0 1292.69
  4732.6 1289.40  4737.7 1289.88  4786.9 1286.95  4797.0 1287.46  4807.0 1286.05
  4818.3 1286.08  4867.5 1282.25  4895.0 1281.01  4938.1 1278.57  4968.3 1275.32
  4974.5 1273.33  4979.6 1275.10  4992.5 1271.97  4993.0 1268.97  5000.4 1268.97
  5000.9 1271.97  5041.4 1276.48  5156.7 1278.98  5276.7 1280.62  5293.8 1281.59
  5360.3 1282.63  5396.8 1284.62  5433.0 1285.90  5626.5 1293.09  5747.0 1297.39
#Mann=11,-1,0
  4377.0    0.05       0  4561.7    0.12       0  4587.6    0.05       0
  4895.0    0.12       0  4992.5    0.07       0  5000.9    0.12       0
  5156.7    0.05       0  5276.7    0.12       0  5396.8    0.05       0
  5433.0    0.12       0  5626.5    0.05       0
Bank Sta=4992.5,5000.9
Exp/Cntr=0.3,0.1

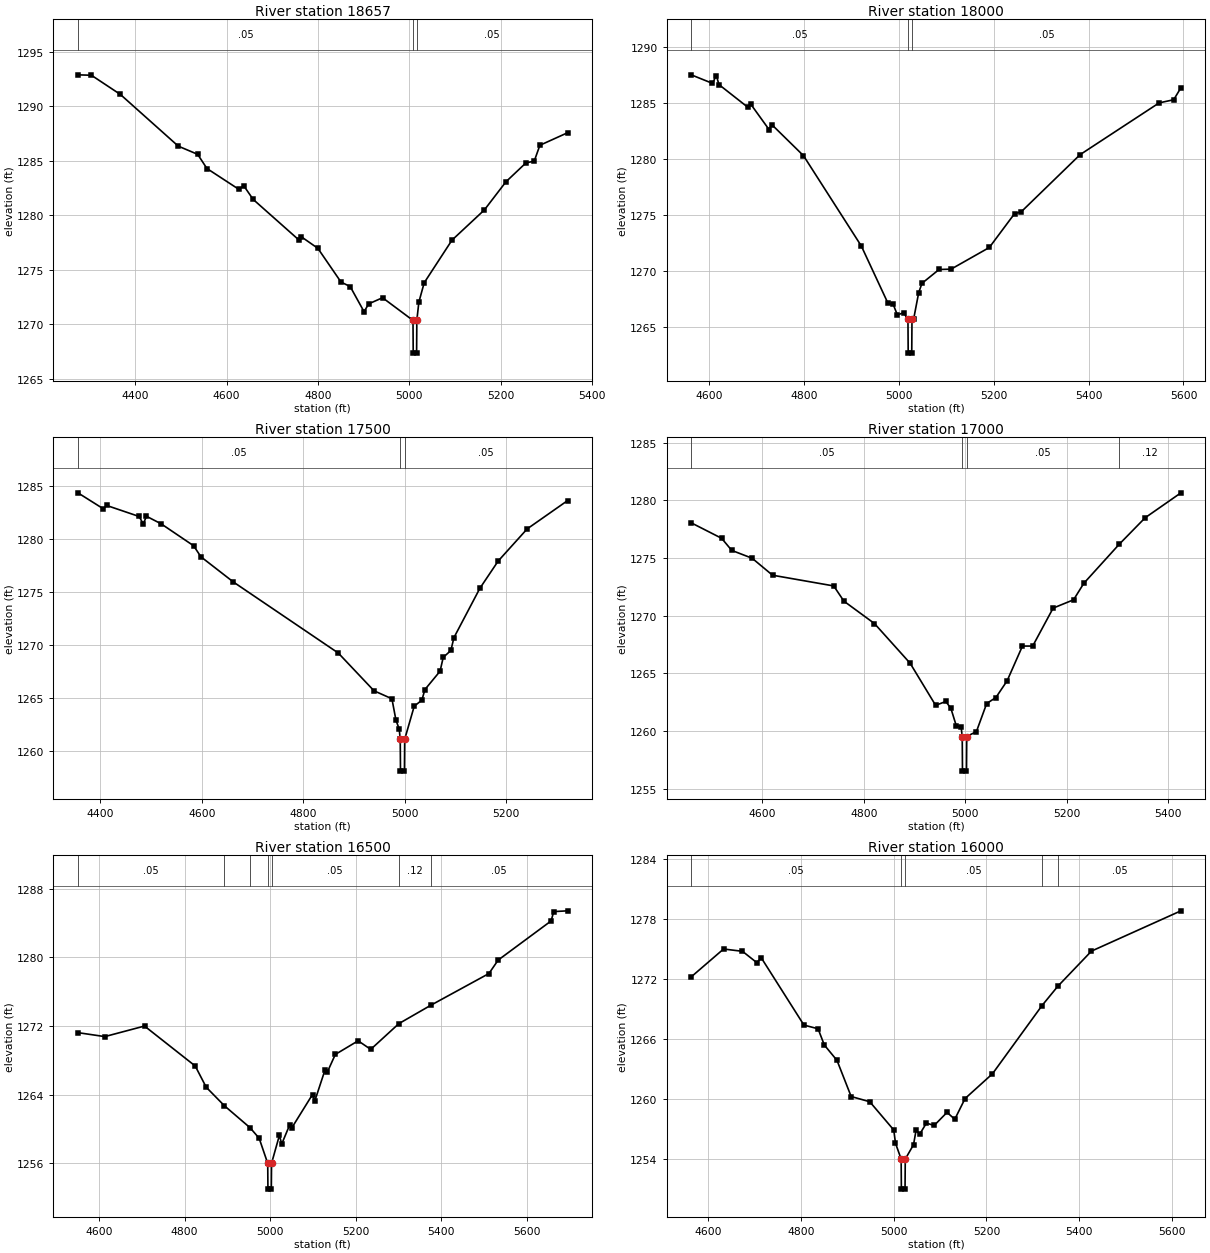
Type RM Length L Ch R = 1,18657,657,657,657
BEGIN DESCRIPTION:
HICKORY13 37.0
END DESCRIPTION:
XS GIS Cut Line= 3
      2726756.57     10208591.85      2727473.50     10208482.00
      2727815.59     10208426.92
#Sta/Elev= 30
  4274.7 1292.87  4304.3 1292.83  4367.7 1291.07  4494.4 1286.33  4536.8 1285.58
  4557.1 1284.28  4626.2 1282.39  4638.0 1282.68  4658.2 1281.45  4758.0 1277.74
  4763.0 1278.04  4799.9 1276.96  4850.5 1273.87  4870.7 1273.45  4901.0 1271.15
  4911.2 1271.87  4941.5 1272.43  5008.1 1270.35  5008.6 1267.35  5016.0 1267.35
  5016.5 1270.35  5020.9 1272.02  5032.6 1273.80  5093.4 1277.71  5164.3 1280.48
  5211.5 1283.06  5255.4 1284.80  5273.4 1284.95  5285.8 1286.41  5346.5 1287.56
#Mann=3,-1,0
  4274.7    0.05       0  5008.1    0.05       0  5016.5    0.05       0
Bank Sta=5008.1,5016.5
Exp/Cntr=0.3,0.1

Type RM Length L Ch R = 1,18000,500,500,500
BEGIN DESCRIPTION:
HICKORY13 36.0
END DESCRIPTION:
XS GIS Cut Line= 3
      2727405.70     10209453.08      2727603.63     10209062.36
      2727805.68     10208503.14
#Sta/Elev= 30
  4562.0 1287.48  4606.8 1286.72  4614.9 1287.42  4620.5 1286.61  4681.7 1284.58
  4687.3 1284.88  4726.2 1282.60  4731.8 1283.05  4798.7 1280.28  4920.7 1272.23
  4976.8 1267.14  4987.9 1267.03  4996.8 1266.08  5009.8 1266.30  5019.0 1265.69
  5019.5 1262.69  5027.0 1262.69  5027.5 1265.69  5031.1 1265.75  5041.7 1268.09
  5048.6 1268.91  5084.6 1270.14  5109.9 1270.17  5190.6 1272.10  5243.7 1275.11
  5257.9 1275.28  5382.0 1280.37  5548.6 1284.98  5579.3 1285.26  5594.6 1286.33
#Mann=3,-1,0
  4562.0    0.05       0  5019.0    0.05       0  5027.5    0.05       0
Bank Sta=5019,5027.5
Exp/Cntr=0.3,0.1

Type RM Length L Ch R = 1,17500,500,500,500
BEGIN DESCRIPTION:
HICKORY13 35.0
END DESCRIPTION:
XS GIS Cut Line= 3
      2727581.22     10209529.33      2728087.23     10209130.16
      2728355.70     10208953.10
#Sta/Elev= 30
  4355.5 1284.33  4405.8 1282.82  4412.2 1283.14  4476.3 1282.10  4484.4 1281.40
  4490.8 1282.12  4519.7 1281.41  4583.8 1279.34  4598.2 1278.30  4662.4 1275.92
  4869.2 1269.23  4939.7 1265.67  4975.0 1264.92  4983.0 1262.89  4989.4 1262.07
  4991.4 1261.10  4991.9 1258.10  4999.7 1258.10  5000.2 1261.10  5019.0 1264.22
  5034.1 1264.79  5040.1 1265.79  5070.0 1267.52  5076.2 1268.82  5091.3 1269.47
  5097.3 1270.68  5148.5 1275.33  5184.6 1277.90  5241.8 1280.93  5321.6 1283.60
#Mann=3,-1,0
  4355.5    0.05       0  4991.4    0.05       0  5000.2    0.05       0
Bank Sta=4991.4,5000.2
Exp/Cntr=0.3,0.1

Type RM Length L Ch R = 1,17000,500,500,500
BEGIN DESCRIPTION:
HICKORY13 34.0
END DESCRIPTION:
XS GIS Cut Line= 3
      2727746.10     10209607.48      2728283.84     10209556.01
      2728705.64     10209503.12
#Sta/Elev= 30
  4459.8 1278.04  4519.7 1276.70  4539.7 1275.65  4579.9 1274.97  4620.1 1273.50
  4740.7 1272.57  4760.8 1271.25  4821.0 1269.31  4891.3 1265.87  4941.6 1262.22
  4961.7 1262.56  4971.7 1261.95  4982.3 1260.45  4991.8 1260.35  4994.0 1259.52
  4994.5 1256.52  5002.4 1256.52  5002.9 1259.52  5022.0 1259.95  5042.2 1262.38
  5060.4 1262.90  5082.5 1264.35  5112.7 1267.36  5132.9 1267.36  5173.2 1270.65
  5213.5 1271.37  5233.7 1272.80  5303.4 1276.18  5354.6 1278.48  5425.1 1280.64
#Mann=4,-1,0
  4459.8    0.05       0  4994.0    0.03       0  5002.9    0.05       0
  5303.4    0.12       0
Bank Sta=4994,5002.9
Exp/Cntr=0.3,0.1

Type RM Length L Ch R = 1,16500,500,500,500
BEGIN DESCRIPTION:
HICKORY13 33.0
END DESCRIPTION:
XS GIS Cut Line= 3
      2727789.53     10209867.89      2728213.06     10210017.29
      2728855.68     10209753.11
#Sta/Elev= 30
  4550.9 1271.22  4613.7 1270.76  4706.5 1271.99  4825.0 1267.33  4850.6 1264.86
  4893.1 1262.70  4953.0 1260.14  4974.3 1258.91  4994.3 1255.98  4994.8 1252.98
  5002.7 1252.98  5003.2 1255.98  5021.6 1259.25  5027.0 1258.24  5045.6 1260.47
  5051.0 1260.16  5098.9 1264.01  5104.3 1263.26  5128.3 1266.90  5133.7 1266.64
  5152.2 1268.68  5205.5 1270.27  5234.9 1269.27  5300.6 1272.27  5374.8 1274.40
  5511.0 1278.11  5532.6 1279.68  5656.2 1284.24  5662.4 1285.33  5694.8 1285.42
#Mann=7,-1,0
  4550.9    0.05       0  4893.1    0.12       0  4953.0    0.05       0
  4994.3    0.03       0  5003.2    0.05       0  5300.6    0.12       0
  5374.8    0.05       0
Bank Sta=4994.3,5003.2
Exp/Cntr=0.3,0.1

Type RM Length L Ch R = 1,16000,500,500,500
BEGIN DESCRIPTION:
HICKORY13 32.0
END DESCRIPTION:
XS GIS Cut Line= 3
      2727937.14     10210492.88      2728365.91     10210409.02
      2728918.04     10210128.29
#Sta/Elev= 30
  4563.1 1272.22  4632.9 1275.00  4673.7 1274.77  4704.3 1273.65  4714.5 1274.10
  4806.2 1267.41  4836.7 1267.04  4850.2 1265.42  4877.5 1263.89  4908.1 1260.28
  4948.2 1259.76  5000.0 1256.94  5003.7 1255.62  5015.9 1254.04  5016.4 1251.04
  5024.3 1251.04  5024.8 1254.04  5042.6 1255.47  5048.2 1256.94  5055.8 1256.51
  5070.4 1257.63  5087.1 1257.39  5114.9 1258.70  5131.6 1258.01  5153.8 1260.08
  5212.9 1262.55  5319.8 1269.36  5353.8 1271.28  5426.4 1274.79  5619.4 1278.81
#Mann=5,-1,0
  4563.1    0.05       0  5015.9    0.03       0  5024.8    0.05       0
  5319.8    0.12       0  5353.8    0.05       0
Bank Sta=5015.9,5024.8
Exp/Cntr=0.3,0.1

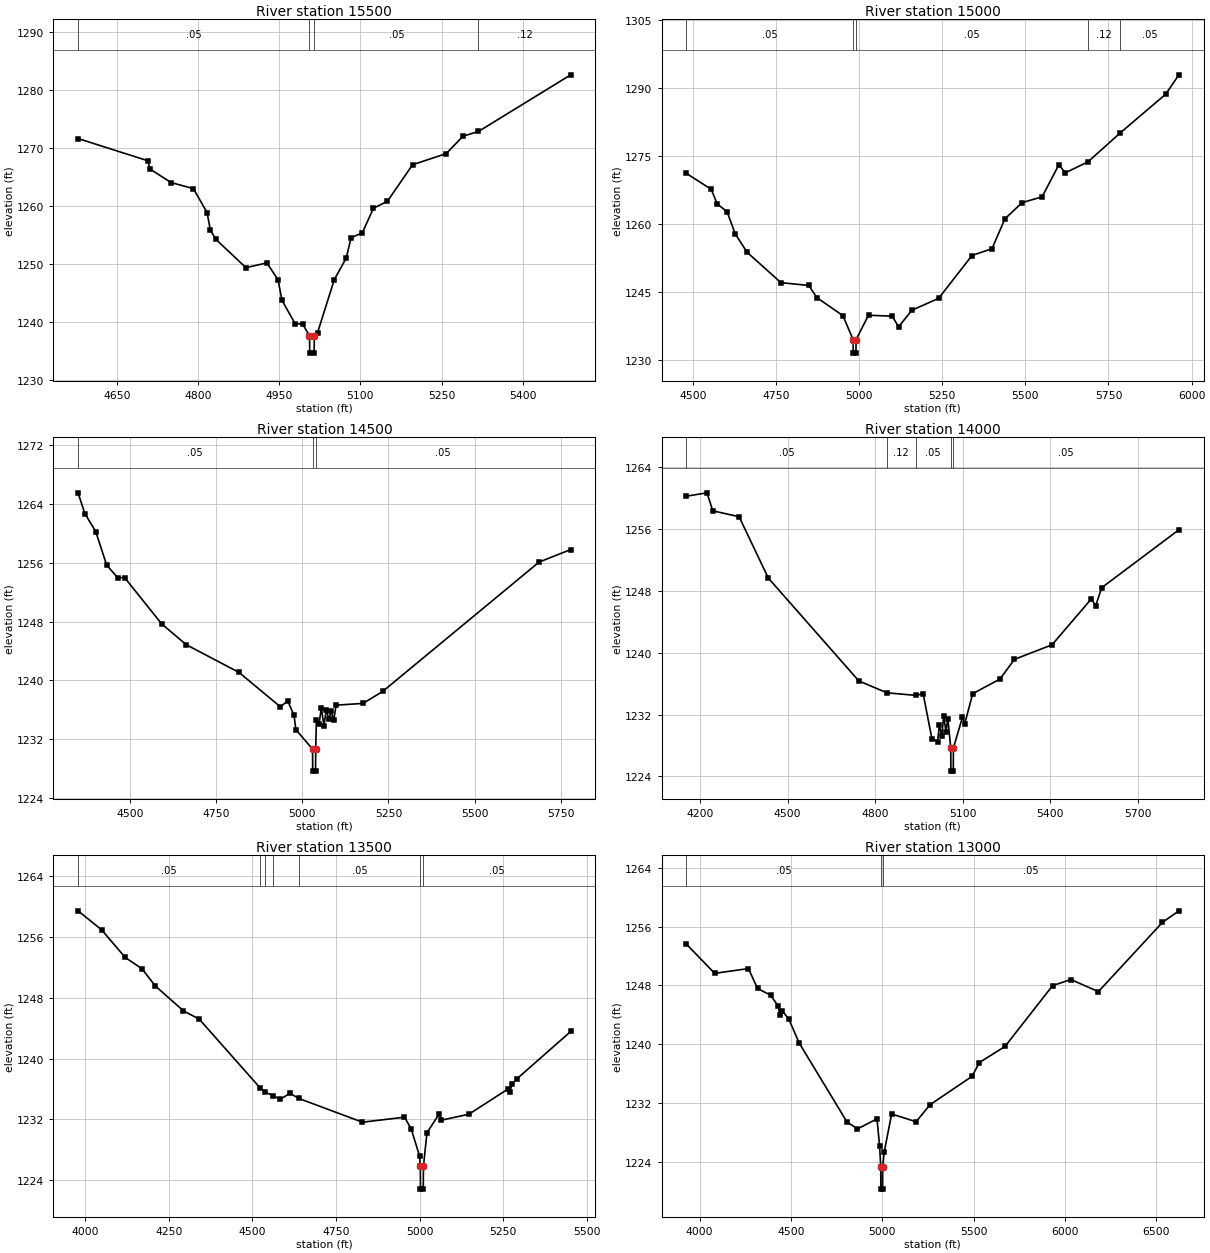
Type RM Length L Ch R = 1,15500,500,500,500
BEGIN DESCRIPTION:
HICKORY13 31.0
END DESCRIPTION:
XS GIS Cut Line= 3
      2728171.45     10210640.45      2728575.51     10210760.43
      2729048.25     10210883.53
#Sta/Elev= 30
  4578.5 1271.66  4706.8 1267.85  4712.1 1266.36  4750.5 1264.06  4791.5 1263.03
  4816.9 1258.89  4822.8 1255.89  4833.3 1254.26  4888.6 1249.39  4927.2 1250.21
  4948.0 1247.30  4955.0 1243.79  4979.3 1239.75  4993.4 1239.65  5006.0 1237.65
  5006.5 1234.65  5014.5 1234.65  5015.0 1237.65  5020.8 1238.15  5051.8 1247.33
  5073.9 1251.05  5082.8 1254.55  5103.5 1255.40  5124.2 1259.65  5149.8 1260.83
  5196.5 1267.15  5258.5 1269.06  5289.5 1272.06  5318.1 1272.88  5488.5 1282.65
#Mann=4,-1,0
  4578.5    0.05       0  5006.0    0.05       0  5015.0    0.05       0
  5318.1    0.12       0
Bank Sta=5006,5015
Exp/Cntr=0.3,0.1

Type RM Length L Ch R = 1,15000,500,500,500
BEGIN DESCRIPTION:
HICKORY13 30.0
END DESCRIPTION:
XS GIS Cut Line= 3
      2728055.70     10210653.16      2728247.47     10211136.39
      2729205.66     10211053.11
#Sta/Elev= 30
  4480.1 1271.14  4555.4 1267.59  4573.2 1264.39  4602.9 1262.66  4627.2 1257.82
  4662.9 1253.74  4764.9 1247.04  4848.6 1246.42  4872.9 1243.75  4951.3 1239.76
  4981.8 1234.51  4982.3 1231.51  4990.4 1231.51  4990.9 1234.51  5028.3 1239.86
  5099.6 1239.65  5118.7 1237.31  5158.8 1240.96  5239.1 1243.58  5339.5 1253.02
  5399.7 1254.53  5438.5 1261.10  5490.1 1264.67  5550.3 1265.95  5600.5 1272.97
  5620.5 1271.25  5688.4 1273.66  5784.3 1279.97  5921.7 1288.54  5961.8 1292.83
#Mann=5,-1,0
  4480.1    0.05       0  4981.8    0.05       0  4990.9    0.05       0
  5688.4    0.12       0  5784.3    0.05       0
Bank Sta=4981.8,4990.9
Exp/Cntr=0.3,0.1

Type RM Length L Ch R = 1,14500,500,500,500
BEGIN DESCRIPTION:
HICKORY13 29.0
END DESCRIPTION:
XS GIS Cut Line= 3
      2727806.88     10210944.25      2728007.26     10211563.44
      2728509.42     10212158.85
#Sta/Elev= 30
  4349.2 1265.54  4369.0 1262.71  4400.6 1260.26  4432.1 1255.70  4463.9 1253.99
  4484.6 1253.97  4592.0 1247.67  4663.3 1244.84  4816.0 1241.07  4936.6 1236.37
  4957.6 1237.20  4976.0 1235.21  4981.3 1233.27  5029.7 1230.61  5030.2 1227.61
  5038.4 1227.61  5038.9 1230.61  5040.8 1234.61  5048.6 1234.05  5055.1 1236.20
  5062.9 1233.78  5069.4 1235.97  5077.2 1234.68  5083.7 1235.78  5091.1 1234.53
  5098.0 1236.60  5176.1 1236.84  5233.2 1238.47  5687.1 1256.10  5778.9 1257.81
#Mann=3,-1,0
  4349.2    0.05       0  5029.7    0.05       0  5038.9    0.05       0
Bank Sta=5029.7,5038.9
Exp/Cntr=0.3,0.1

Type RM Length L Ch R = 1,14000,500,500,500
BEGIN DESCRIPTION:
HICKORY13 28.0
END DESCRIPTION:
XS GIS Cut Line= 3
      2727668.00     10210892.16      2727641.09     10211738.63
      2728305.72     10212253.14
#Sta/Elev= 30
  4153.1 1260.24  4224.1 1260.68  4244.1 1258.35  4334.1 1257.59  4434.2 1249.65
  4744.4 1236.34  4840.8 1234.81  4939.0 1234.48  4964.5 1234.69  4994.5 1228.87
  5013.8 1228.50  5020.1 1230.60  5028.3 1229.22  5034.6 1231.79  5042.8 1229.80
  5049.1 1231.47  5059.0 1227.68  5059.5 1224.68  5067.7 1224.68  5068.2 1227.68
  5098.9 1231.62  5107.0 1230.81  5134.2 1234.70  5227.5 1236.59  5277.3 1239.14
  5405.9 1241.02  5540.8 1246.97  5555.2 1246.05  5576.1 1248.41  5840.5 1255.90
#Mann=5,-1,0
  4153.1    0.05       0  4840.8    0.12       0  4939.0    0.05       0
  5059.0    0.05       0  5068.2    0.05       0
Bank Sta=5059,5068.2
Exp/Cntr=0.3,0.1

Type RM Length L Ch R = 1,13500,500,500,500
BEGIN DESCRIPTION:
HICKORY13 27.0
END DESCRIPTION:
XS GIS Cut Line= 3
      2727055.68     10210803.11      2727169.74     10211817.92
      2727555.71     10212053.13
#Sta/Elev= 30
  3978.8 1259.47  4049.2 1256.97  4119.7 1253.33  4170.0 1251.83  4210.3 1249.55
  4294.0 1246.29  4341.1 1245.20  4523.6 1236.12  4539.3 1235.55  4562.9 1235.12
  4582.6 1234.62  4612.8 1235.43  4638.7 1234.75  4829.3 1231.62  4954.9 1232.28
  4975.0 1230.74  5000.0 1227.16  5002.3 1225.80  5002.8 1222.80  5011.1 1222.80
  5011.6 1225.80  5022.1 1230.23  5058.8 1232.71  5065.5 1231.89  5147.5 1232.67
  5264.1 1235.98  5269.9 1235.55  5276.3 1236.67  5291.2 1237.34  5452.0 1243.57
#Mann=7,-1,0
  3978.8    0.05       0  4523.6    0.12       0  4539.3    0.05       0
  4562.9    0.12       0  4638.7    0.05       0  5002.3    0.05       0
  5011.6    0.05       0
Bank Sta=5002.3,5011.6
Exp/Cntr=0.3,0.1

Type RM Length L Ch R = 1,13000,500,500,500
BEGIN DESCRIPTION:
HICKORY13 26.0
END DESCRIPTION:
XS GIS Cut Line= 3
      2725955.72     10211453.14      2726785.26     10212134.66
      2728405.64     10212253.11
#Sta/Elev= 30
  3926.4 1253.64  4082.1 1249.64  4267.2 1250.29  4316.7 1247.58  4388.4 1246.67
  4431.1 1245.14  4437.9 1243.94  4452.3 1244.50  4487.5 1243.45  4544.9 1240.16
  4806.8 1229.41  4864.2 1228.47  4971.1 1229.83  4985.4 1226.14  4991.7 1223.27
  4992.2 1220.27  5001.8 1220.27  5002.3 1223.27  5010.5 1225.31  5051.4 1230.50
  5185.2 1229.44  5261.1 1231.75  5491.7 1235.62  5531.8 1237.50  5672.2 1239.69
  5932.9 1247.97  6033.2 1248.80  6183.6 1247.15  6534.5 1256.58  6624.7 1258.15
#Mann=3,-1,0
  3926.4    0.05       0  4991.7    0.05       0  5002.3    0.05       0
Bank Sta=4991.7,5002.3
Exp/Cntr=0.3,0.1

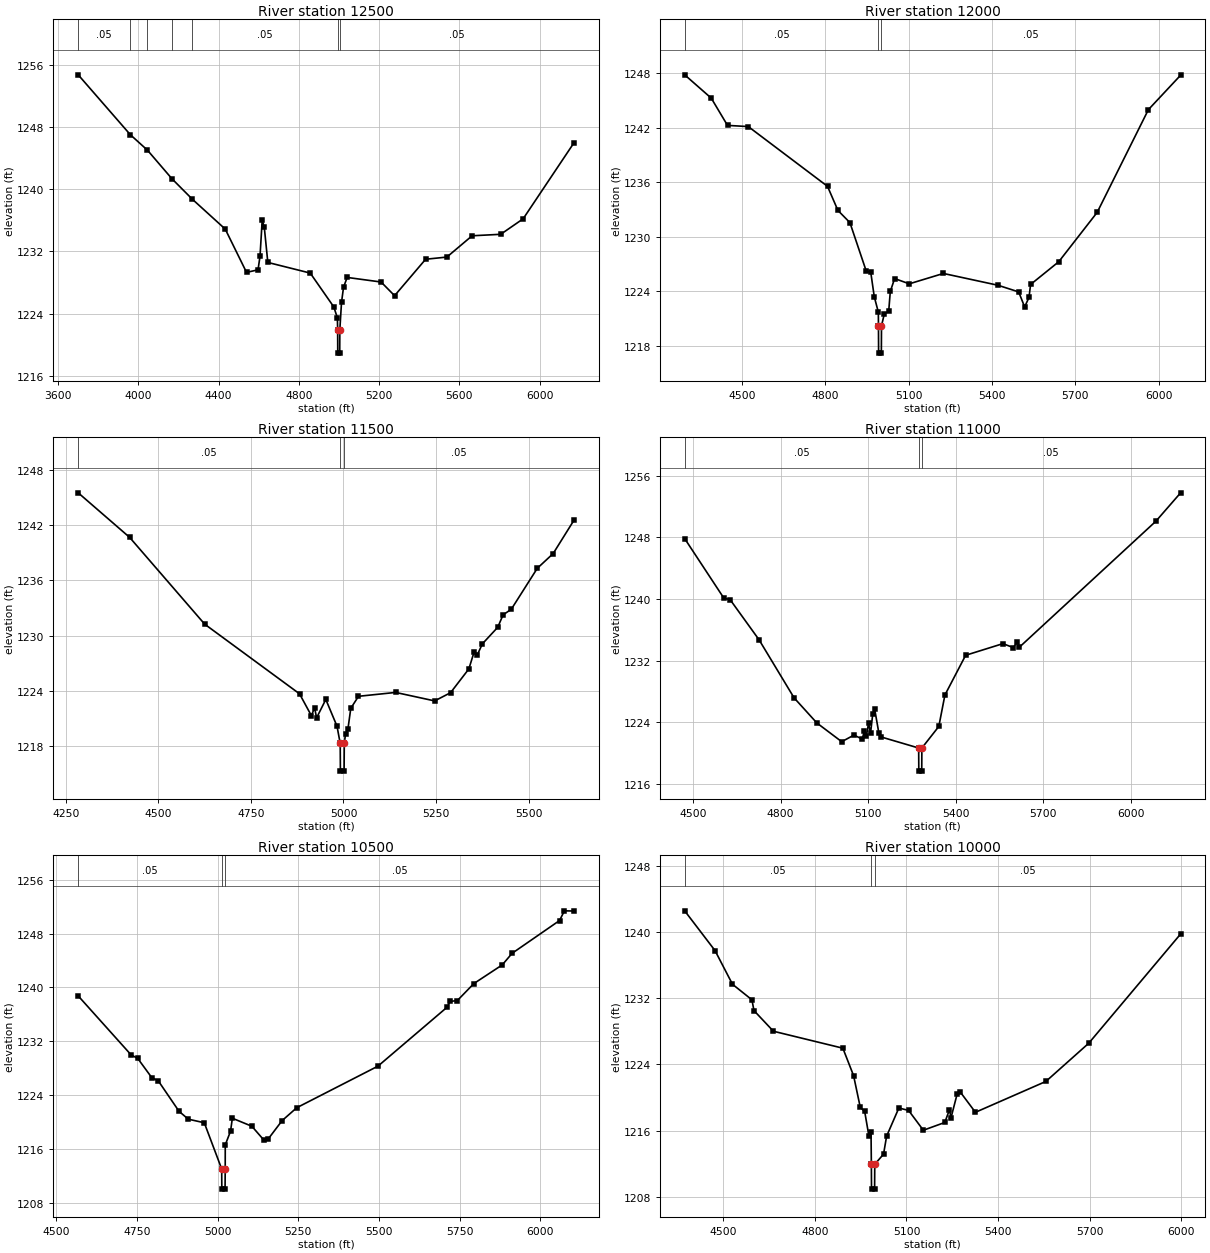
Type RM Length L Ch R = 1,12500,500,500,500
BEGIN DESCRIPTION:
HICKORY13 25.0
END DESCRIPTION:
XS GIS Cut Line= 3
      2725254.78     10212055.38      2726503.44     10212416.03
      2727655.73     10212203.10
#Sta/Elev= 30
  3700.3 1254.73  3960.2 1247.02  4045.1 1245.04  4167.3 1241.36  4268.8 1238.73
  4433.0 1234.88  4539.1 1229.31  4596.4 1229.64  4606.3 1231.39  4617.2 1236.02
  4627.6 1235.12  4645.2 1230.59  4856.6 1229.22  4973.9 1224.87  4991.9 1223.46
  4993.2 1221.92  4993.7 1218.92  5003.5 1218.92  5004.0 1221.92  5012.5 1225.46
  5022.6 1227.41  5040.7 1228.66  5209.7 1228.07  5276.9 1226.31  5431.6 1231.00
  5537.5 1231.28  5663.3 1234.02  5805.7 1234.21  5917.5 1236.20  6171.8 1246.02
#Mann=7,-1,0
  3700.3    0.05       0  3960.2    0.12       0  4045.1    0.05       0
  4167.3    0.12       0  4268.8    0.05       0  4993.2    0.03       0
  5004.0    0.05       0
Bank Sta=4993.2,5004
Exp/Cntr=0.3,0.1

Type RM Length L Ch R = 1,12000,500,500,500
BEGIN DESCRIPTION:
HICKORY13 24.0
END DESCRIPTION:
XS GIS Cut Line= 3
      2726426.67     10213366.18      2726776.57     10212752.41
      2727705.64     10212203.14
#Sta/Elev= 30
  4293.5 1247.80  4389.1 1245.24  4447.7 1242.24  4522.6 1242.11  4807.8 1235.54
  4845.3 1232.89  4888.5 1231.55  4947.6 1226.19  4963.4 1226.12  4976.2 1223.40
  4990.8 1221.71  4991.3 1220.20  4991.8 1217.20  5001.7 1217.20  5002.2 1220.20
  5012.4 1221.52  5028.1 1221.78  5033.9 1223.98  5049.5 1225.40  5102.2 1224.82
  5225.1 1225.96  5422.0 1224.66  5496.2 1223.93  5517.6 1222.28  5533.3 1223.32
  5539.1 1224.75  5640.5 1227.25  5778.9 1232.68  5963.2 1243.97  6079.3 1247.76
#Mann=3,-1,0
  4293.5    0.05       0  4991.3    0.05       0  5002.2    0.05       0
Bank Sta=4991.3,5002.2
Exp/Cntr=0.3,0.1

Type RM Length L Ch R = 1,11500,500,500,500
BEGIN DESCRIPTION:
HICKORY13 23.0
END DESCRIPTION:
XS GIS Cut Line= 3
      2727005.70     10213503.08      2727256.83     10212831.92
      2727655.70     10212353.09
#Sta/Elev= 30
  4283.4 1245.50  4422.2 1240.67  4625.0 1231.25  4881.3 1223.69  4913.3 1221.32
  4922.0 1222.18  4927.4 1221.08  4952.3 1223.08  4982.6 1220.17  4991.2 1218.30
  4991.7 1215.30  5001.7 1215.30  5002.2 1218.30  5005.5 1219.32  5012.0 1219.86
  5019.8 1222.12  5040.6 1223.42  5140.9 1223.84  5246.3 1222.92  5289.3 1223.81
  5338.7 1226.39  5353.1 1228.25  5360.9 1227.85  5375.2 1229.11  5416.8 1230.91
  5431.2 1232.26  5453.3 1232.86  5523.6 1237.31  5566.5 1238.91  5623.2 1242.56
#Mann=3,-1,0
  4283.4    0.05       0  4991.2    0.03       0  5002.2    0.05       0
Bank Sta=4991.2,5002.2
Exp/Cntr=0.3,0.1

Type RM Length L Ch R = 1,11000,500,500,500
BEGIN DESCRIPTION:
HICKORY13 22.0
END DESCRIPTION:
XS GIS Cut Line= 3
      2727155.68     10213603.11      2727520.32     10213220.41
      2728305.65     10212353.15
#Sta/Elev= 30
  4471.4 1247.83  4605.9 1240.08  4626.9 1239.91  4726.0 1234.70  4846.2 1227.15
  4924.2 1223.89  5009.3 1221.46  5051.2 1222.32  5079.5 1221.80  5087.0 1222.89
  5093.7 1222.19  5101.2 1223.87  5107.9 1222.54  5115.4 1225.02  5122.1 1225.69
  5136.3 1222.62  5143.8 1222.08  5272.8 1220.64  5273.3 1217.64  5283.3 1217.64
  5283.8 1220.64  5341.8 1223.44  5362.7 1227.52  5433.7 1232.68  5561.4 1234.19
  5596.6 1233.68  5610.8 1234.40  5617.5 1233.72  6085.2 1250.08  6170.0 1253.77
#Mann=3,-1,0
  4471.4    0.05       0  5272.8    0.03       0  5283.8    0.05       0
Bank Sta=5272.8,5283.8
Exp/Cntr=0.3,0.1

Type RM Length L Ch R = 1,10500,500,500,500
BEGIN DESCRIPTION:
HICKORY13 21.0
END DESCRIPTION:
XS GIS Cut Line= 3
      2727555.68     10213803.11      2727889.95     10213529.92
      2728405.68     10212553.11
#Sta/Elev= 30
  4568.3 1238.73  4732.0 1229.98  4752.8 1229.44  4795.9 1226.61  4816.7 1226.09
  4880.6 1221.59  4909.3 1220.42  4958.8 1219.89  5012.7 1213.03  5013.2 1210.03
  5023.2 1210.03  5023.7 1213.03  5023.8 1216.60  5040.2 1218.64  5045.8 1220.56
  5106.2 1219.37  5143.4 1217.32  5155.9 1217.42  5200.0 1220.21  5245.2 1222.12
  5496.9 1228.30  5711.4 1237.07  5720.1 1237.91  5742.7 1238.04  5793.8 1240.56
  5881.9 1243.34  5912.4 1245.06  6059.4 1249.93  6074.4 1251.37  6104.6 1251.34
#Mann=3,-1,0
  4568.3    0.05       0  5012.7    0.05       0  5023.7    0.05       0
Bank Sta=5012.7,5023.7
Exp/Cntr=0.3,0.1

Type RM Length L Ch R = 1,10000,500,500,500
BEGIN DESCRIPTION:
HICKORY13 20.0
END DESCRIPTION:
XS GIS Cut Line= 3
      2727755.71     10214253.09      2728233.16     10213847.93
      2728305.69     10212853.07
#Sta/Elev= 30
  4373.8 1242.58  4473.2 1237.77  4530.3 1233.70  4594.0 1231.82  4600.6 1230.52
  4664.3 1228.02  4891.7 1225.97  4926.8 1222.65  4948.8 1218.80  4963.1 1218.33
  4977.1 1215.32  4983.9 1215.80  4985.0 1211.93  4985.5 1208.93  4995.6 1208.93
  4996.1 1211.93  5024.9 1213.16  5034.9 1215.33  5075.0 1218.74  5106.8 1218.45
  5155.2 1216.05  5225.4 1216.99  5240.7 1218.53  5245.7 1217.55  5265.5 1220.38
  5275.5 1220.70  5325.7 1218.22  5556.3 1221.95  5696.7 1226.57  5997.5 1239.78
#Mann=3,-1,0
  4373.8    0.05       0  4985.0    0.03       0  4996.1    0.05       0
Bank Sta=4985,4996.1
Exp/Cntr=0.3,0.1

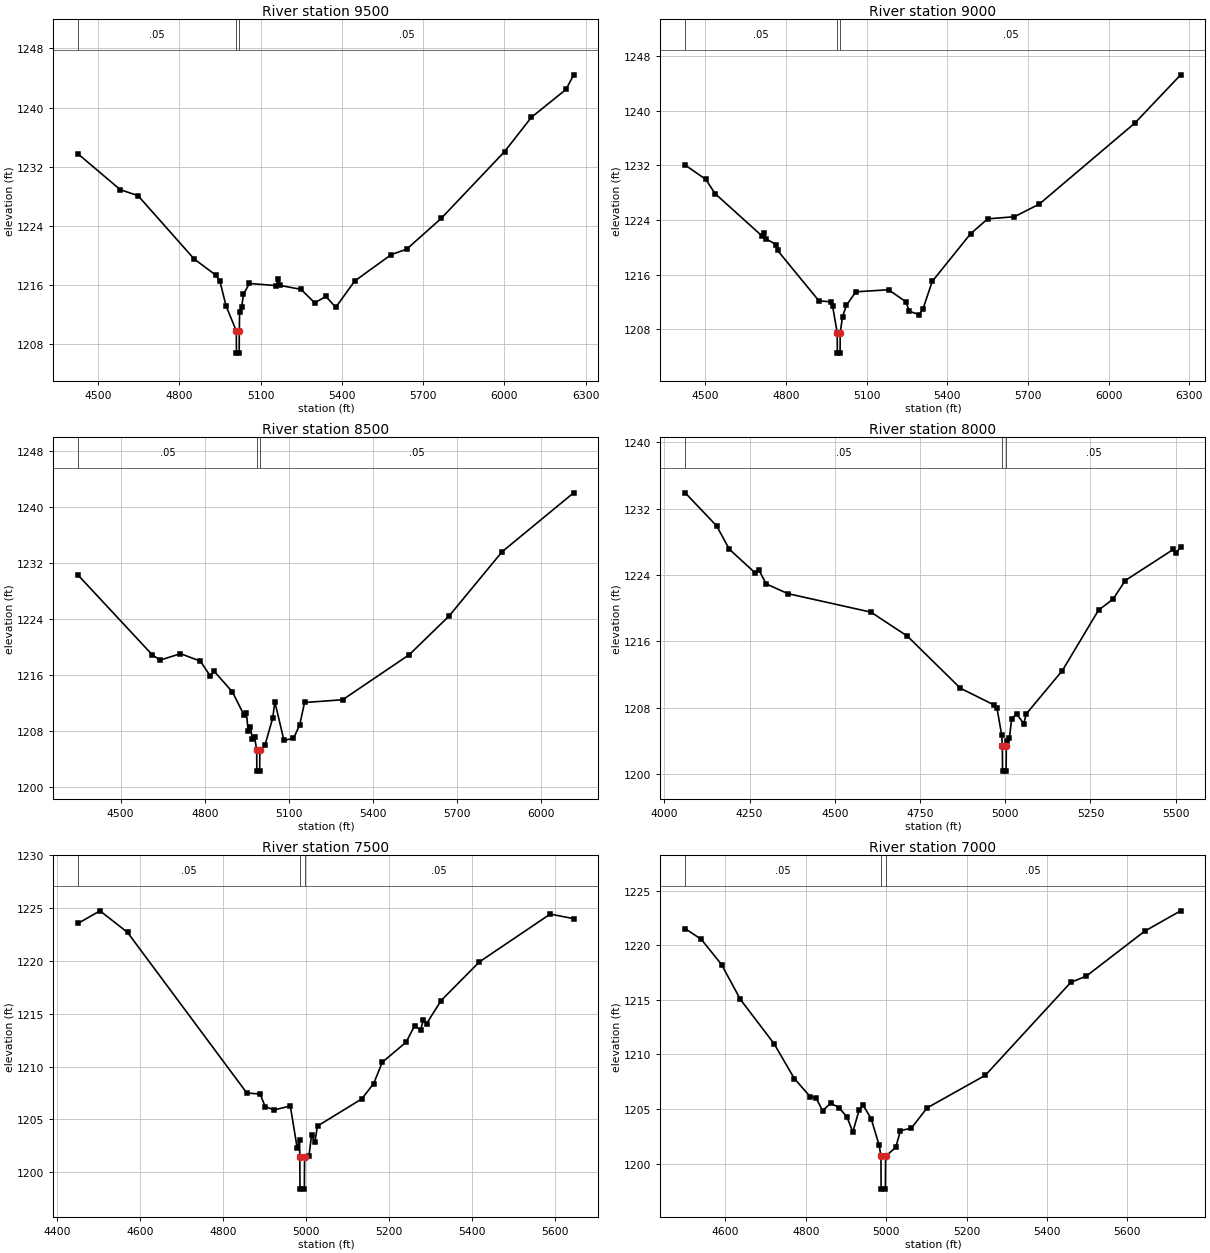
Type RM Length L Ch R = 1,9500,500,500,500
BEGIN DESCRIPTION:
HICKORY13 19.0
END DESCRIPTION:
XS GIS Cut Line= 3
      2728055.65     10214353.13      2728560.13     10214079.11
      2729505.67     10213253.13
#Sta/Elev= 30
  4425.9 1233.71  4581.3 1228.89  4646.9 1228.08  4854.1 1219.52  4935.8 1217.29
  4949.4 1216.48  4972.2 1213.14  5009.8 1209.79  5010.3 1206.79  5020.4 1206.79
  5020.9 1209.79  5022.0 1212.39  5029.6 1213.02  5036.2 1214.74  5058.1 1216.21
  5156.8 1215.92  5164.4 1216.79  5171.0 1215.95  5248.9 1215.41  5299.2 1213.59
  5340.9 1214.45  5377.0 1212.98  5447.3 1216.55  5582.0 1220.11  5639.0 1220.85
  5766.2 1225.00  6000.7 1234.05  6099.4 1238.67  6227.5 1242.45  6255.5 1244.42
#Mann=3,-1,0
  4425.9    0.05       0  5009.8    0.03       0  5020.9    0.05       0
Bank Sta=5009.8,5020.9
Exp/Cntr=0.3,0.1

Type RM Length L Ch R = 1,9000,500,500,500
BEGIN DESCRIPTION:
HICKORY13 18.0
END DESCRIPTION:
XS GIS Cut Line= 3
      2728705.68     10214903.13      2728951.96     10214383.44
      2729755.70     10213403.09
#Sta/Elev= 30
  4424.9 1232.03  4501.7 1229.93  4535.6 1227.87  4712.0 1221.61  4717.5 1222.11
  4723.7 1221.27  4763.0 1220.40  4768.5 1219.54  4922.2 1212.17  4967.2 1212.02
  4973.2 1211.39  4990.3 1207.52  4990.8 1204.52  5001.0 1204.52  5001.5 1207.52
  5010.3 1209.87  5024.7 1211.53  5059.8 1213.49  5181.1 1213.79  5245.0 1212.06
  5259.0 1210.64  5294.5 1210.16  5308.9 1210.94  5344.0 1215.03  5486.1 1221.97
  5550.0 1224.16  5649.1 1224.47  5741.6 1226.31  6097.6 1238.18  6267.7 1245.23
#Mann=3,-1,0
  4424.9    0.05       0  4990.3    0.03       0  5001.5    0.05       0
Bank Sta=4990.3,5001.5
Exp/Cntr=0.3,0.1

Type RM Length L Ch R = 1,8500,500,500,500
BEGIN DESCRIPTION:
HICKORY13 17.0
END DESCRIPTION:
XS GIS Cut Line= 3
      2728855.71     10214953.09      2729373.01     10214558.04
      2729855.67     10213553.14
#Sta/Elev= 30
  4349.1 1230.24  4613.3 1218.87  4641.1 1218.12  4713.7 1219.04  4784.4 1217.98
  4819.8 1215.86  4834.3 1216.50  4898.7 1213.58  4940.4 1210.25  4948.6 1210.58
  4954.9 1207.99  4963.1 1208.62  4969.4 1206.92  4977.7 1207.19  4985.2 1205.27
  4985.7 1202.27  4995.9 1202.27  4996.4 1205.27  5014.4 1205.93  5042.6 1209.87
  5049.8 1212.19  5082.3 1206.68  5116.4 1206.93  5138.7 1208.89  5155.8 1212.07
  5291.6 1212.46  5529.1 1218.90  5671.1 1224.43  5859.7 1233.59  6114.8 1242.01
#Mann=3,-1,0
  4349.1    0.05       0  4985.2    0.03       0  4996.4    0.05       0
Bank Sta=4985.2,4996.4
Exp/Cntr=0.3,0.1

Type RM Length L Ch R = 1,8000,500,500,500
BEGIN DESCRIPTION:
HICKORY13 16.0
END DESCRIPTION:
XS GIS Cut Line= 3
      2728955.73     10215103.09      2729825.46     10214749.93
      2730205.65     10214403.14
#Sta/Elev= 30
  4061.3 1233.89  4153.6 1229.90  4190.8 1227.09  4266.3 1224.25  4277.1 1224.63
  4298.7 1222.92  4362.5 1221.74  4606.2 1219.51  4713.3 1216.61  4868.6 1210.34
  4967.9 1208.31  4975.8 1207.95  4989.5 1204.75  4991.7 1203.35  4992.2 1200.35
  5002.7 1200.35  5003.2 1203.35  5004.9 1204.02  5012.3 1204.33  5019.1 1206.68
  5033.3 1207.25  5054.4 1206.07  5061.6 1207.24  5167.7 1212.47  5273.8 1219.76
  5316.3 1221.07  5352.1 1223.32  5493.4 1227.08  5500.8 1226.58  5514.6 1227.38
#Mann=3,-1,0
  4061.3    0.05       0  4991.7    0.03       0  5003.2    0.05       0
Bank Sta=4991.7,5003.2
Exp/Cntr=0.3,0.1

Type RM Length L Ch R = 1,7500,500,500,500
BEGIN DESCRIPTION:
HICKORY13 15.0
END DESCRIPTION:
XS GIS Cut Line= 3
      2729405.66     10215453.12      2729893.69     10215200.58
      2730305.67     10214703.13
#Sta/Elev= 30
  4450.5 1223.57  4503.1 1224.75  4569.5 1222.71  4857.3 1207.51  4889.6 1207.41
  4901.6 1206.21  4923.7 1205.91  4962.3 1206.28  4978.9 1202.29  4984.5 1203.10
  4985.2 1201.41  4985.7 1198.41  4996.2 1198.41  4996.7 1201.41  5007.1 1201.50
  5013.6 1203.52  5021.4 1202.87  5027.9 1204.38  5134.7 1206.95  5163.4 1208.40
  5184.2 1210.42  5241.5 1212.31  5262.3 1213.88  5276.7 1213.46  5283.2 1214.40
  5291.0 1214.07  5326.2 1216.26  5418.6 1219.92  5589.3 1224.44  5645.9 1224.01
#Mann=3,-1,0
  4450.5    0.05       0  4985.2    0.03       0  4996.7    0.05       0
Bank Sta=4985.2,4996.7
Exp/Cntr=0.3,0.1

Type RM Length L Ch R = 1,7000,500,500,500
BEGIN DESCRIPTION:
HICKORY13 14.0
END DESCRIPTION:
XS GIS Cut Line= 3
      2729555.67     10215603.11      2730053.05     10215657.14
      2730255.68     10214953.12
#Sta/Elev= 30
  4499.7 1221.51  4539.9 1220.53  4590.2 1218.22  4637.1 1215.03  4721.0 1210.97
  4771.3 1207.79  4811.5 1206.10  4825.2 1206.02  4841.7 1204.85  4861.8 1205.53
  4881.9 1205.14  4902.1 1204.29  4916.8 1202.90  4932.2 1204.87  4942.3 1205.36
  4962.4 1204.12  4982.5 1201.67  4986.8 1200.67  4987.3 1197.67  4997.9 1197.67
  4998.4 1200.67  5023.7 1201.50  5035.4 1203.02  5062.6 1203.25  5101.5 1205.10
  5246.6 1208.09  5459.2 1216.59  5498.0 1217.17  5643.2 1221.28  5732.6 1223.14
#Mann=3,-1,0
  4499.7    0.05       0  4986.8    0.03       0  4998.4    0.05       0
Bank Sta=4986.8,4998.4
Exp/Cntr=0.3,0.1