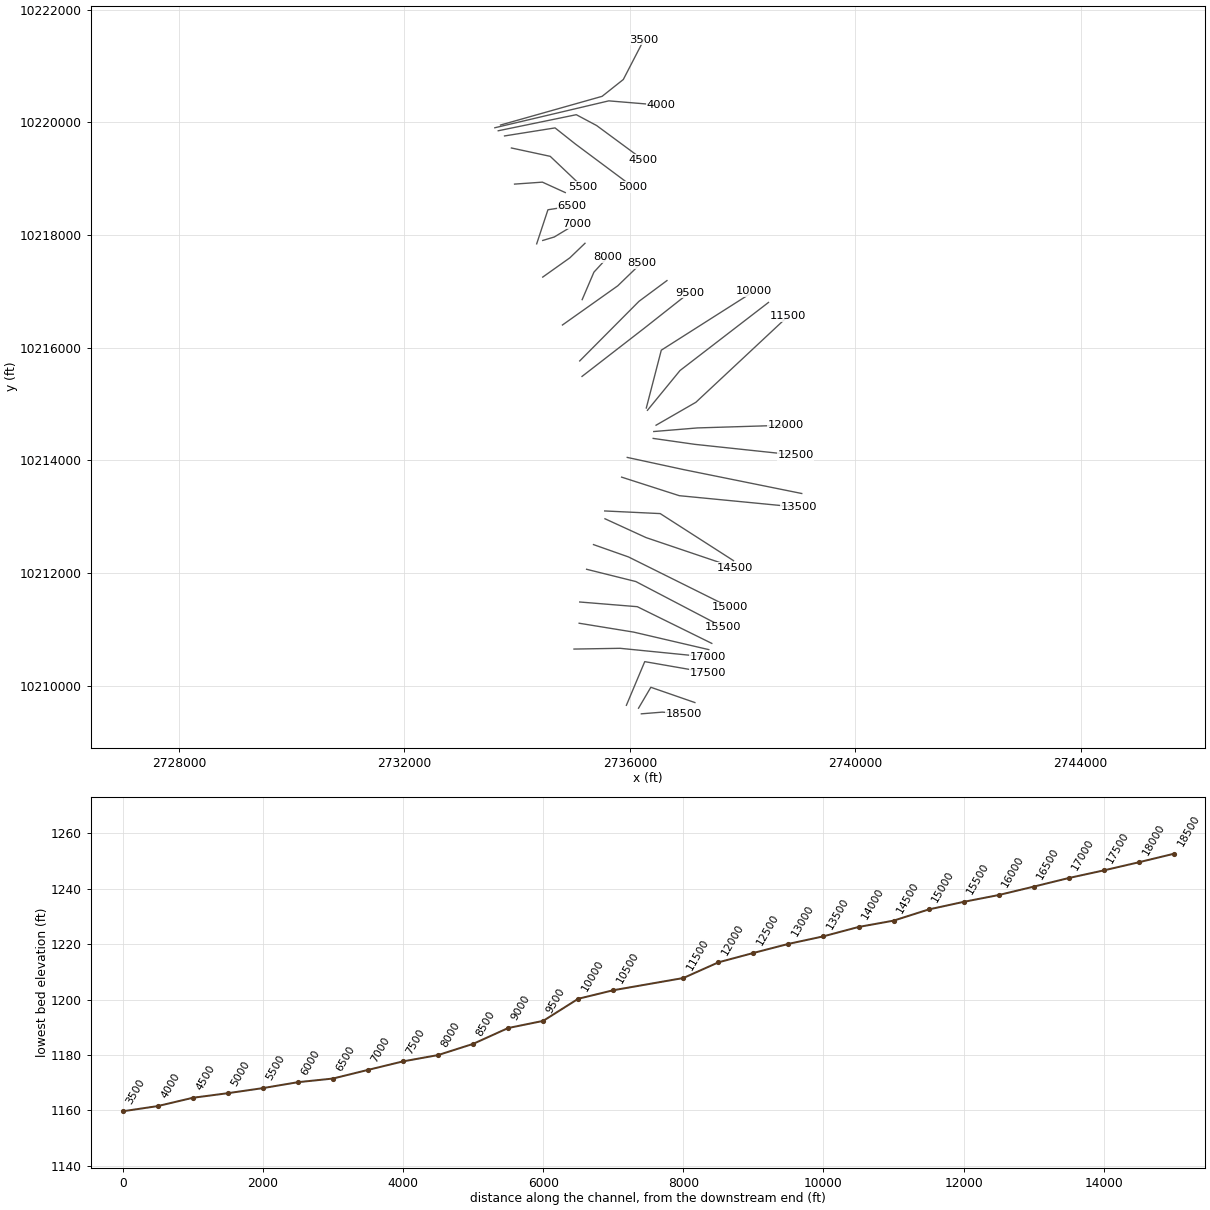
HEC-RAS study LANG CREEK.prj: LANG CREEK Base Level Engineering

--- LANG CREEK.g01 (geometry) --- (continued)

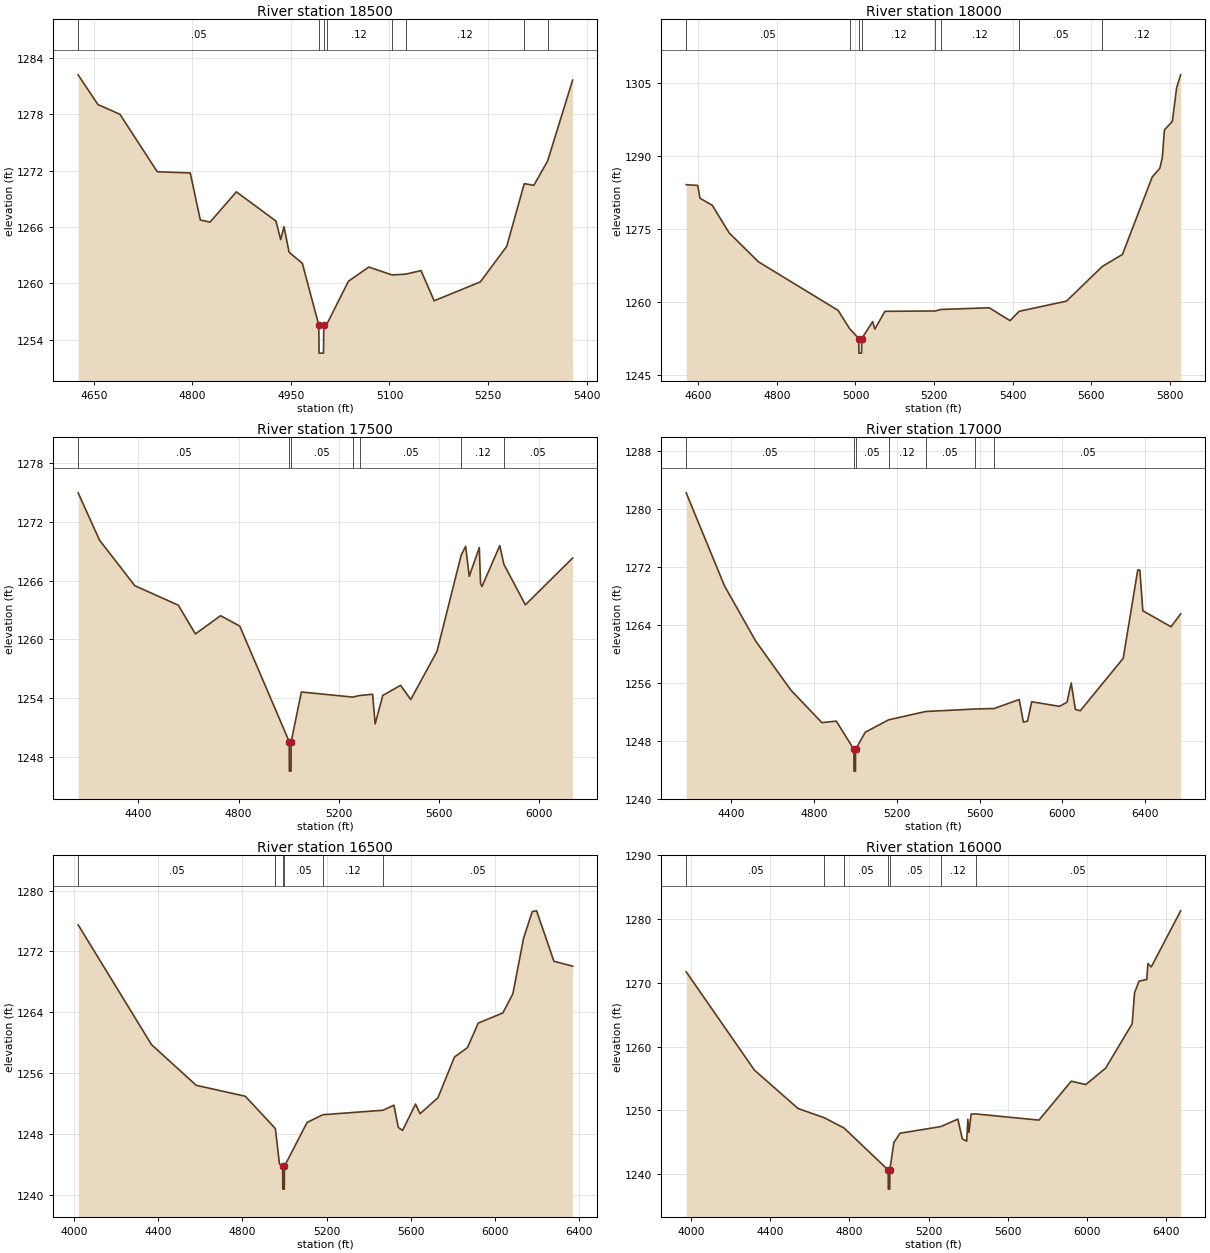
Type RM Length L Ch R = 1,18500,500,500,500
BEGIN DESCRIPTION:
LANG CREEK 36.0
END DESCRIPTION:
XS GIS Cut Line= 3
      2736205.68     10209503.11      2736578.17     10209533.22
      2736955.67     10209503.11
#Sta/Elev= 30
  4626.3 1282.18  4656.4 1279.02  4689.9 1277.98  4746.7 1271.87  4796.9 1271.74
  4812.2 1266.74  4827.0 1266.51  4867.1 1269.73  4927.3 1266.62  4934.5 1264.65
  4939.5 1266.03  4947.3 1263.30  4967.4 1262.13  4992.4 1255.57  4992.9 1252.57
  4999.6 1252.57  5000.1 1255.57  5004.5 1255.62  5037.6 1260.22  5068.5 1261.73
  5103.9 1260.89  5124.5 1260.97  5148.0 1261.35  5168.0 1258.14  5238.3 1260.15
  5278.4 1263.93  5305.1 1270.60  5319.7 1270.43  5340.6 1273.01  5378.7 1281.62
#Mann=8,-1,0
  4626.3    0.05       0  4992.4    0.05       0  5000.1    0.05       0
  5004.5    0.12       0  5103.9    0.05       0  5124.5    0.12       0
  5305.1    0.05       0  5340.6    0.12       0
Bank Sta=4992.4,5000.1
Exp/Cntr=0.3,0.1

Type RM Length L Ch R = 1,18000,500,500,500
BEGIN DESCRIPTION:
LANG CREEK 35.0
END DESCRIPTION:
XS GIS Cut Line= 3
      2736155.68     10209603.10      2736374.19     10209974.15
      2737155.72     10209703.10
#Sta/Elev= 30
  4569.4 1284.16  4598.7 1284.00  4604.5 1281.37  4635.8 1279.91  4678.7 1274.24
  4753.0 1268.30  4955.9 1258.29  4984.9 1254.55  5008.3 1252.50  5008.8 1249.50
  5015.5 1249.50  5016.0 1252.50  5043.8 1255.99  5049.1 1254.43  5074.9 1258.10
  5203.4 1258.17  5216.7 1258.48  5340.3 1258.83  5393.2 1256.18  5416.4 1258.11
  5536.7 1260.20  5627.9 1267.34  5679.0 1269.80  5754.6 1285.71  5774.2 1287.54
  5780.5 1289.76  5785.8 1295.43  5806.0 1297.19  5816.9 1304.13  5827.2 1306.76
#Mann=8,-1,0
  4569.4    0.05       0  4984.9    0.12       0  5008.3    0.07       0
  5016.0    0.12       0  5203.4    0.05       0  5216.7    0.12       0
  5416.4    0.05       0  5627.9    0.12       0
Bank Sta=5008.3,5016
Exp/Cntr=0.3,0.1

Type RM Length L Ch R = 1,17500,500,500,500
BEGIN DESCRIPTION:
LANG CREEK 34.0
END DESCRIPTION:
XS GIS Cut Line= 3
      2735940.35     10209654.54      2736265.97     10210429.29
      2737382.09     10210235.00
#Sta/Elev= 30
  4159.6 1274.95  4244.8 1270.13  4385.8 1265.48  4559.4 1263.49  4627.5 1260.56
  4727.9 1262.42  4804.6 1261.36  5002.0 1249.57  5002.5 1246.57  5009.2 1246.57
  5009.7 1249.57  5050.5 1254.64  5255.0 1254.12  5283.9 1254.28  5334.7 1254.41
  5344.8 1251.38  5375.3 1254.29  5446.3 1255.32  5486.9 1253.87  5591.7 1258.79
  5687.9 1268.57  5705.9 1269.50  5720.4 1266.44  5760.4 1269.36  5765.5 1265.70
  5771.1 1265.40  5842.2 1269.57  5858.6 1267.66  5944.3 1263.53  6132.9 1268.30
#Mann=7,-1,0
  4159.6    0.05       0  5002.0    0.05       0  5009.7    0.05       0
  5255.0    0.12       0  5283.9    0.05       0  5687.9    0.12       0
  5858.6    0.05       0
Bank Sta=5002,5009.7
Exp/Cntr=0.3,0.1

Type RM Length L Ch R = 1,17000,500,500,500
BEGIN DESCRIPTION:
LANG CREEK 33.0
END DESCRIPTION:
XS GIS Cut Line= 3
      2735010.30     10210652.35      2735828.59     10210665.73
      2737392.15     10210509.91
#Sta/Elev= 30
  4181.6 1282.18  4367.0 1269.34  4517.0 1261.77  4687.1 1255.00  4837.1 1250.51
  4907.1 1250.71  4992.1 1246.82  4992.6 1243.82  4999.4 1243.82  4999.9 1246.82
  5047.3 1249.19  5159.8 1250.89  5339.0 1252.04  5576.3 1252.38  5669.7 1252.45
  5791.0 1253.69  5811.1 1250.58  5831.2 1250.71  5851.3 1253.38  5985.7 1252.75
  6022.1 1253.32  6042.2 1255.97  6062.3 1252.32  6086.3 1252.15  6293.5 1259.37
  6363.8 1271.55  6373.9 1271.53  6388.4 1265.92  6524.6 1263.72  6571.3 1265.50
#Mann=7,-1,0
  4181.6    0.05       0  4992.1    0.05       0  4999.9    0.05       0
  5159.8    0.12       0  5339.0    0.05       0  5576.3    0.12       0
  5669.7    0.05       0
Bank Sta=4992.1,4999.9
Exp/Cntr=0.3,0.1

Type RM Length L Ch R = 1,16500,500,500,500
BEGIN DESCRIPTION:
LANG CREEK 32.0
END DESCRIPTION:
XS GIS Cut Line= 3
      2735101.95     10211110.70      2736069.31     10210953.17
      2737402.29     10210642.53
#Sta/Elev= 30
  4019.9 1275.49  4368.2 1259.73  4580.9 1254.37  4814.0 1252.93  4956.5 1248.69
  4956.8 1248.65  4976.1 1244.05  4991.5 1243.71  4992.0 1240.71  4999.2 1240.71
  4999.7 1243.71  5107.2 1249.48  5181.8 1250.50  5468.3 1251.09  5519.9 1251.76
  5540.5 1248.83  5561.0 1248.44  5622.6 1251.90  5643.7 1250.63  5728.8 1252.73
  5807.4 1258.09  5869.1 1259.33  5920.4 1262.56  6037.1 1263.89  6084.8 1266.41
  6136.0 1273.76  6177.1 1277.24  6197.6 1277.33  6279.8 1270.69  6368.7 1270.05
#Mann=7,-1,0
  4019.9    0.05       0  4956.5    0.12       0  4956.8    0.05       0
  4991.5    0.05       0  4999.7    0.05       0  5181.8    0.12       0
  5468.3    0.05       0
Bank Sta=4991.5,4999.7
Exp/Cntr=0.3,0.1

Type RM Length L Ch R = 1,16000,500,500,500
BEGIN DESCRIPTION:
LANG CREEK 31.0
END DESCRIPTION:
XS GIS Cut Line= 3
      2735112.22     10211487.54      2736133.63     10211404.27
      2737455.67     10210753.12
#Sta/Elev= 30
  3975.2 1271.73  4319.8 1256.33  4540.5 1250.31  4673.9 1248.85  4773.4 1247.24
  4995.9 1240.68  4996.4 1237.68  5003.6 1237.68  5004.1 1240.68  5024.6 1244.98
  5055.8 1246.44  5260.8 1247.47  5347.8 1248.65  5370.1 1245.55  5392.4 1245.20
  5398.3 1248.62  5403.9 1246.55  5414.7 1249.45  5438.7 1249.46  5757.8 1248.49
  5920.6 1254.59  5994.4 1254.06  6094.7 1256.64  6228.5 1263.58  6240.6 1268.44
  6263.1 1270.26  6302.5 1270.53  6308.0 1273.02  6324.9 1272.49  6473.7 1281.28
#Mann=7,-1,0
  3975.2    0.05       0  4673.9    0.12       0  4773.4    0.05       0
  4995.9    0.05       0  5004.1    0.05       0  5260.8    0.12       0
  5438.7    0.05       0
Bank Sta=4995.9,5004.1
Exp/Cntr=0.3,0.1

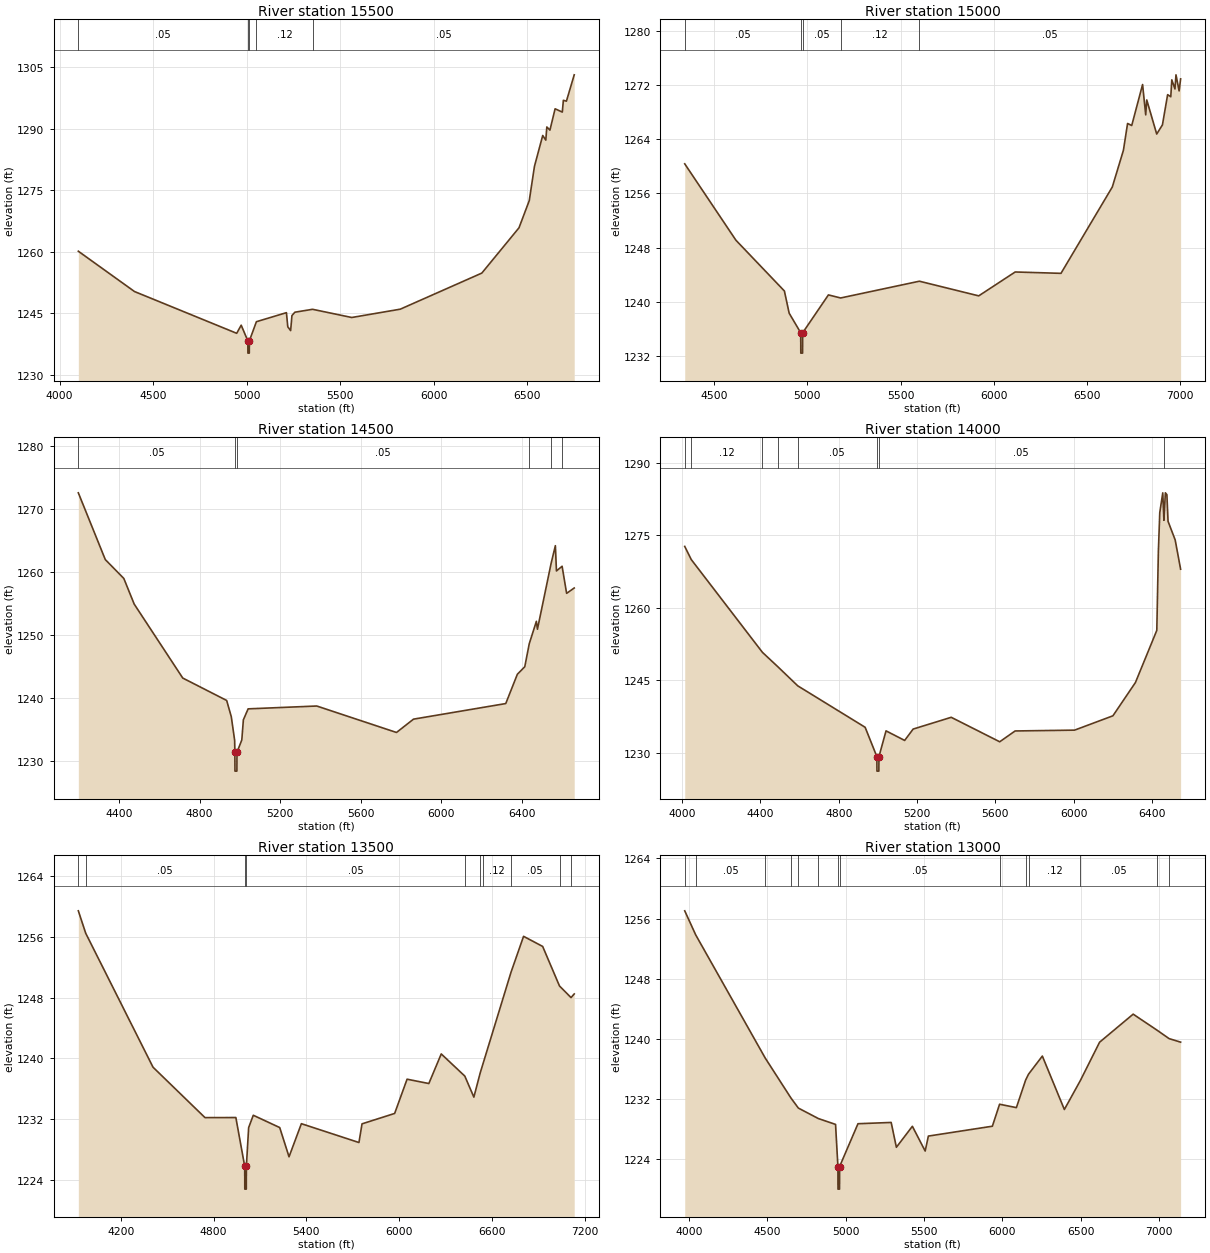
Type RM Length L Ch R = 1,15500,500,500,500
BEGIN DESCRIPTION:
LANG CREEK 30.0
END DESCRIPTION:
XS GIS Cut Line= 3
      2735234.44     10212068.09      2736107.95     10211850.50
      2737658.51     10211039.38
#Sta/Elev= 30
  4099.8 1260.10  4399.9 1250.26  4946.1 1240.06  4970.2 1242.04  5005.6 1238.22
  5006.1 1235.22  5013.4 1235.22  5013.9 1238.22  5051.4 1242.89  5211.9 1245.10
  5219.2 1241.65  5234.4 1240.72  5241.3 1244.39  5257.0 1245.21  5351.4 1245.92
  5561.1 1243.92  5820.3 1245.95  6256.1 1254.76  6454.8 1265.82  6509.7 1272.46
  6537.4 1280.82  6581.6 1288.36  6598.0 1287.23  6603.6 1290.44  6620.1 1289.67
  6647.8 1294.88  6686.3 1294.07  6691.9 1296.95  6708.3 1296.74  6749.9 1303.17
#Mann=5,-1,0
  4099.8    0.05       0  5005.6    0.05       0  5013.9    0.05       0
  5051.4    0.12       0  5351.4    0.05       0
Bank Sta=5005.6,5013.9
Exp/Cntr=0.3,0.1

Type RM Length L Ch R = 1,15000,500,500,500
BEGIN DESCRIPTION:
LANG CREEK 29.0
END DESCRIPTION:
XS GIS Cut Line= 3
      2735356.60     10212506.07      2735977.02     10212287.18
      2737770.55     10211395.86
#Sta/Elev= 30
  4342.1 1260.37  4616.8 1249.11  4876.8 1241.63  4902.4 1238.36  4964.4 1235.47
  4964.9 1232.47  4974.4 1232.47  4974.9 1235.47  5113.0 1241.05  5178.6 1240.60
  5601.1 1243.07  5919.5 1240.91  6115.2 1244.43  6360.9 1244.23  6636.3 1256.96
  6695.9 1262.37  6718.2 1266.32  6740.5 1266.02  6798.7 1272.06  6815.5 1267.59
  6821.1 1269.79  6874.5 1264.76  6905.2 1266.11  6933.1 1270.57  6950.0 1270.26
  6955.5 1272.75  6972.4 1271.41  6977.9 1273.49  6994.8 1271.12  7002.8 1272.89
#Mann=5,-1,0
  4342.1    0.05       0  4964.4    0.03       0  4974.9    0.05       0
  5178.6    0.12       0  5601.1    0.05       0
Bank Sta=4964.4,4974.9
Exp/Cntr=0.3,0.1

Type RM Length L Ch R = 1,14500,500,500,500
BEGIN DESCRIPTION:
LANG CREEK 28.0
END DESCRIPTION:
XS GIS Cut Line= 3
      2735560.31     10212964.40      2736289.12     10212630.39
      2737861.42     10212098.91
#Sta/Elev= 30
  4198.3 1272.51  4332.1 1261.94  4424.1 1258.95  4475.6 1254.89  4716.6 1243.18
  4934.6 1239.63  4957.6 1237.05  4974.2 1233.31  4975.3 1231.44  4975.8 1228.44
  4985.3 1228.44  4985.8 1231.44  5009.7 1233.37  5017.5 1236.56  5041.1 1238.30
  5381.8 1238.75  5777.5 1234.56  5862.0 1236.67  6319.9 1239.14  6377.5 1243.78
  6414.3 1244.97  6436.5 1248.61  6471.9 1252.16  6477.2 1250.91  6545.1 1261.35
  6566.2 1264.14  6571.5 1260.14  6599.6 1260.88  6622.0 1256.59  6659.7 1257.44
#Mann=6,-1,0
  4198.3    0.05       0  4975.3    0.05       0  4985.8    0.05       0
  6436.5    0.12       0  6545.1    0.05       0  6599.6    0.12       0
Bank Sta=4975.3,4985.8
Exp/Cntr=0.3,0.1

Type RM Length L Ch R = 1,14000,500,500,500
BEGIN DESCRIPTION:
LANG CREEK 27.0
END DESCRIPTION:
XS GIS Cut Line= 3
      2735555.66     10213103.11      2736540.75     10213056.28
      2737841.24     10212221.24
#Sta/Elev= 30
  4013.8 1272.71  4047.2 1269.98  4410.6 1250.76  4490.3 1247.74  4590.7 1243.83
  4934.9 1235.24  4994.7 1229.16  4995.2 1226.16  5004.8 1226.16  5005.3 1229.16
  5041.5 1234.50  5136.6 1232.52  5179.9 1234.87  5374.3 1237.31  5621.9 1232.24
  5700.5 1234.48  6004.1 1234.65  6199.9 1237.62  6314.9 1244.52  6423.9 1255.32
  6431.9 1271.65  6439.1 1279.71  6454.3 1283.80  6458.5 1279.76  6460.2 1278.12
  6467.6 1283.81  6475.4 1283.43  6481.3 1277.91  6517.7 1274.06  6545.5 1267.99
#Mann=8,-1,0
  4013.8    0.05       0  4047.2    0.12       0  4410.6    0.05       0
  4490.3    0.12       0  4590.7    0.05       0  4994.7    0.03       0
  5005.3    0.05       0  6458.5    0.12       0
Bank Sta=4994.7,5005.3
Exp/Cntr=0.3,0.1

Type RM Length L Ch R = 1,13500,500,500,500
BEGIN DESCRIPTION:
LANG CREEK 26.0
END DESCRIPTION:
XS GIS Cut Line= 3
      2735855.69     10213703.11      2736879.29     10213374.02
      2739001.73     10213168.21
#Sta/Elev= 30
  3924.8 1259.45  3972.7 1256.49  4408.0 1238.85  4744.1 1232.21  4943.7 1232.22
  5001.1 1225.79  5001.6 1222.79  5011.2 1222.79  5011.7 1225.79  5026.5 1230.89
  5056.4 1232.52  5227.5 1230.90  5287.7 1227.05  5367.6 1231.41  5739.9 1228.93
  5759.9 1231.39  5970.9 1232.76  6051.3 1237.27  6192.0 1236.70  6272.3 1240.60
  6424.7 1237.68  6483.3 1234.91  6524.3 1238.10  6539.6 1239.12  6723.6 1251.36
  6804.8 1256.09  6928.3 1254.76  7037.2 1249.55  7111.9 1248.02  7132.4 1248.50
#Mann=10,-1,0
  3924.8    0.12       0  3972.7    0.05       0  5001.1    0.05       0
  5011.7    0.05       0  6424.7    0.12       0  6524.3    0.05       0
  6539.6    0.12       0  6723.6    0.05       0  7037.2    0.12       0
  7111.9    0.05       0
Bank Sta=5001.1,5011.7
Exp/Cntr=0.3,0.1

Type RM Length L Ch R = 1,13000,500,500,500
BEGIN DESCRIPTION:
LANG CREEK 25.0
END DESCRIPTION:
XS GIS Cut Line= 3
      2735955.70     10214053.11      2736958.60     10213836.15
      2739052.24     10213412.86
#Sta/Elev= 30
  3973.9 1257.04  4043.7 1253.85  4487.1 1237.48  4651.8 1232.15  4698.5 1230.83
  4825.8 1229.44  4935.6 1228.66  4950.7 1223.06  4951.2 1220.06  4960.9 1220.06
  4961.4 1223.06  5078.6 1228.75  5290.3 1228.92  5323.5 1225.62  5425.5 1228.41
  5507.1 1225.12  5527.5 1227.11  5935.6 1228.42  5981.6 1231.34  6088.7 1230.89
  6147.7 1234.55  6166.1 1235.33  6254.3 1237.74  6394.7 1230.64  6497.2 1234.51
  6619.2 1239.58  6833.4 1243.31  6982.9 1241.22  7062.5 1240.06  7136.0 1239.59
#Mann=14,-1,0
  3973.9    0.12       0  4043.7    0.05       0  4487.1    0.12       0
  4651.8    0.05       0  4698.5    0.12       0  4825.8    0.05       0
  4950.7    0.05       0  4961.4    0.05       0  5981.6    0.12       0
  6147.7    0.05       0  6166.1    0.12       0  6497.2    0.05       0
  6982.9    0.12       0  7062.5    0.05       0
Bank Sta=4950.7,4961.4
Exp/Cntr=0.3,0.1

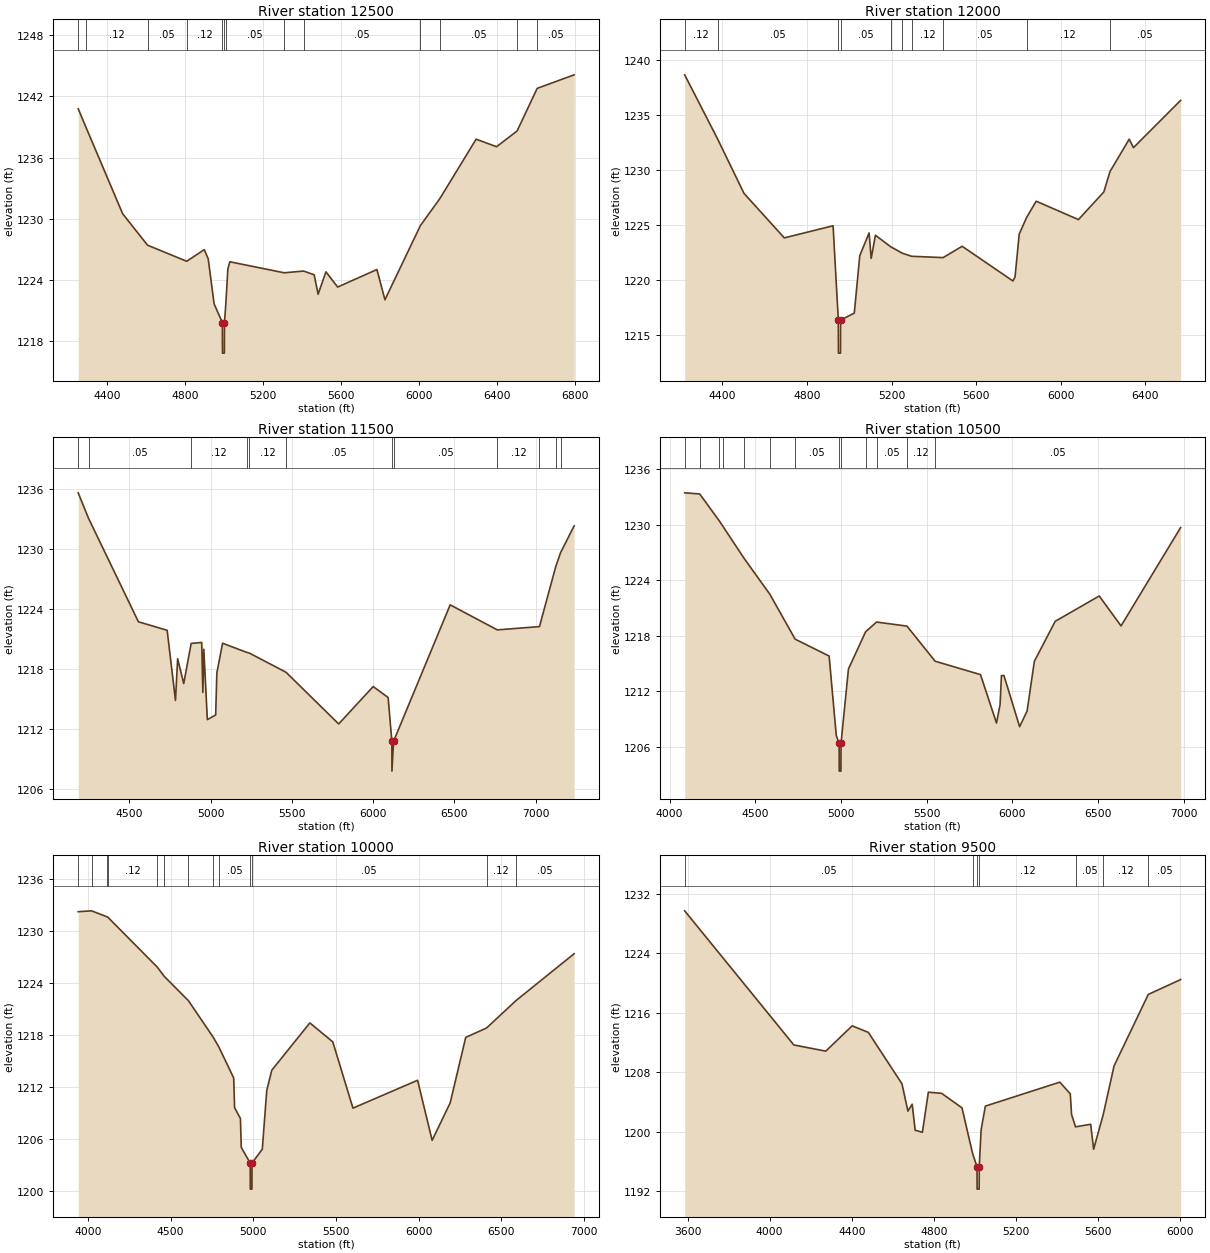
Type RM Length L Ch R = 1,12500,500,500,500
BEGIN DESCRIPTION:
LANG CREEK 24.0
END DESCRIPTION:
XS GIS Cut Line= 3
      2736415.88     10214390.32      2737155.23     10214285.06
      2738941.25     10214095.01
#Sta/Elev= 30
  4253.2 1240.79  4292.1 1239.01  4481.0 1230.48  4608.8 1227.39  4809.5 1225.81
  4899.4 1226.95  4919.7 1226.06  4950.0 1221.63  4992.4 1219.79  4992.9 1216.79
  5002.6 1216.79  5003.1 1219.79  5010.2 1221.67  5020.6 1225.07  5030.6 1225.76
  5309.5 1224.68  5409.3 1224.85  5463.1 1224.48  5483.2 1222.57  5523.4 1224.77
  5583.7 1223.28  5784.9 1225.00  5825.9 1222.03  6007.9 1229.32  6107.7 1231.97
  6293.5 1237.80  6398.3 1237.06  6503.8 1238.61  6606.5 1242.79  6796.1 1244.12
#Mann=13,-1,0
  4253.2    0.05       0  4292.1    0.12       0  4608.8    0.05       0
  4809.5    0.12       0  4992.4    0.07       0  5003.1    0.12       0
  5010.2    0.05       0  5309.5    0.12       0  5409.3    0.05       0
  6007.9    0.12       0  6107.7    0.05       0  6503.8    0.12       0
  6606.5    0.05       0
Bank Sta=4992.4,5003.1
Exp/Cntr=0.3,0.1

Type RM Length L Ch R = 1,12000,500,500,500
BEGIN DESCRIPTION:
LANG CREEK 23.0
END DESCRIPTION:
XS GIS Cut Line= 3
      2736426.06     10214512.54      2737202.13     10214576.56
      2738768.69     10214624.58
#Sta/Elev= 30
  4221.3 1238.66  4377.3 1232.83  4501.9 1227.90  4692.5 1223.86  4923.3 1224.96
  4948.1 1216.40  4948.6 1213.40  4958.3 1213.40  4958.8 1216.40  5023.6 1217.03
  5049.6 1222.25  5093.6 1224.31  5103.6 1222.00  5123.6 1224.10  5196.3 1223.05
  5250.6 1222.47  5294.8 1222.19  5443.9 1222.07  5533.8 1223.10  5773.9 1219.95
  5783.9 1220.30  5803.9 1224.21  5838.5 1225.70  5884.0 1227.19  6084.1 1225.52
  6204.1 1228.03  6233.2 1229.88  6324.2 1232.82  6344.2 1232.05  6567.3 1236.34
#Mann=10,-1,0
  4221.3    0.12       0  4377.3    0.05       0  4948.1    0.03       0
  4958.8    0.05       0  5196.3    0.12       0  5250.6    0.05       0
  5294.8    0.12       0  5443.9    0.05       0  5838.5    0.12       0
  6233.2    0.05       0
Bank Sta=4948.1,4958.8
Exp/Cntr=0.3,0.1

Type RM Length L Ch R = 1,11500,1000,1000,1000
BEGIN DESCRIPTION:
LANG CREEK 22.0
END DESCRIPTION:
XS GIS Cut Line= 3
      2736466.82     10214624.58      2737173.50     10215031.57
      2738808.49     10216558.91
#Sta/Elev= 30
  4184.5 1235.65  4247.9 1233.10  4555.2 1222.72  4732.0 1221.87  4783.3 1214.84
  4796.6 1219.02  4834.0 1216.53  4879.8 1220.55  4944.8 1220.65  4951.8 1215.65
  4957.6 1219.97  4979.4 1212.91  5030.7 1213.38  5038.0 1217.60  5073.2 1220.57
  5221.5 1219.66  5237.3 1219.59  5464.0 1217.66  5787.9 1212.48  6000.4 1216.23
  6092.3 1215.13  6115.2 1210.75  6115.7 1207.75  6126.0 1210.75  6474.3 1224.42
  6764.2 1221.91  7023.9 1222.24  7124.5 1228.28  7153.8 1229.65  7237.4 1232.34
#Mann=12,-1,0
  4184.5    0.12       0  4247.9    0.05       0  4879.8    0.12       0
  5221.5    0.05       0  5237.3    0.12       0  5464.0    0.05       0
  6115.2    0.07       0  6126.0    0.05       0  6764.2    0.12       0
  7023.9    0.05       0  7124.5    0.12       0  7153.8    0.05       0
Bank Sta=6115.2,6126
Exp/Cntr=0.3,0.1

Type RM Length L Ch R = 1,10500,500,500,500
BEGIN DESCRIPTION:
LANG CREEK 21.0
END DESCRIPTION:
XS GIS Cut Line= 3
      2736314.07     10214889.43      2736891.85     10215595.18
      2738461.86     10216803.25
#Sta/Elev= 30
  4087.9 1233.47  4175.5 1233.35  4290.4 1230.42  4310.7 1229.85  4436.2 1226.33
  4584.2 1222.51  4732.2 1217.63  4930.6 1215.80  4972.3 1207.19  4989.1 1206.34
  4989.6 1203.34  4999.4 1203.34  4999.9 1206.34  5043.3 1214.40  5143.5 1218.43
  5207.4 1219.48  5384.6 1219.04  5548.9 1215.24  5813.5 1213.79  5906.9 1208.55
  5927.7 1210.54  5935.9 1213.68  5950.4 1213.69  6041.8 1208.15  6085.4 1209.84
  6127.8 1215.23  6249.4 1219.56  6506.3 1222.30  6633.5 1219.06  6981.0 1229.71
#Mann=13,-1,0
  4087.9    0.05       0  4175.5    0.12       0  4290.4    0.05       0
  4310.7    0.12       0  4436.2    0.05       0  4584.2    0.12       0
  4732.2    0.05       0  4989.1    0.05       0  4999.9    0.05       0
  5143.5    0.12       0  5207.4    0.05       0  5384.6    0.12       0
  5548.9    0.05       0
Bank Sta=4989.1,4999.9
Exp/Cntr=0.3,0.1

Type RM Length L Ch R = 1,10000,500,500,500
BEGIN DESCRIPTION:
LANG CREEK 20.0
END DESCRIPTION:
XS GIS Cut Line= 3
      2736293.67     10214930.16      2736559.65     10215955.83
      2738198.27     10216997.71
#Sta/Elev= 30
  3940.4 1232.22  4021.4 1232.32  4117.3 1231.61  4120.0 1231.58  4419.3 1225.83
  4459.7 1224.80  4607.4 1221.97  4758.4 1217.73  4791.9 1216.62  4881.5 1213.06
  4886.7 1209.64  4922.1 1208.40  4927.2 1205.07  4981.4 1203.26  4981.9 1200.26
  4991.8 1200.26  4992.3 1203.26  5054.4 1204.86  5081.5 1211.63  5112.0 1213.96
  5342.3 1219.41  5481.2 1217.22  5603.1 1209.59  5994.3 1212.80  6082.4 1205.88
  6191.6 1210.20  6285.6 1217.74  6411.4 1218.82  6591.1 1222.00  6941.8 1227.38
#Mann=13,-1,0
  3940.4    0.05       0  4021.4    0.12       0  4117.3    0.05       0
  4120.0    0.12       0  4419.3    0.05       0  4459.7    0.12       0
  4607.4    0.05       0  4758.4    0.12       0  4791.9    0.05       0
  4981.4    0.05       0  4992.3    0.05       0  6411.4    0.12       0
  6591.1    0.05       0
Bank Sta=4981.4,4992.3
Exp/Cntr=0.3,0.1

Type RM Length L Ch R = 1,9500,500,500,500
BEGIN DESCRIPTION:
LANG CREEK 19.0
END DESCRIPTION:
XS GIS Cut Line= 3
      2735152.96     10215490.34      2736270.62     10216356.17
      2737057.58     10216977.38
#Sta/Elev= 30
  3586.2 1229.70  4118.0 1211.67  4273.7 1210.84  4402.3 1214.24  4481.0 1213.36
  4644.9 1206.45  4673.9 1202.78  4694.7 1203.71  4709.2 1200.21  4744.5 1199.93
  4773.5 1205.32  4837.8 1205.17  4937.3 1203.22  4989.0 1197.09  5010.6 1195.29
  5011.1 1192.29  5021.0 1192.29  5021.5 1195.29  5030.5 1200.26  5051.3 1203.45
  5414.1 1206.67  5465.0 1205.10  5471.3 1202.31  5490.6 1200.66  5564.3 1201.01
  5578.8 1197.66  5625.8 1202.34  5678.2 1208.84  5845.0 1218.46  6002.6 1220.46
#Mann=7,-1,0
  3586.2    0.05       0  4989.0    0.12       0  5010.6    0.07       0
  5021.5    0.12       0  5490.6    0.05       0  5625.8    0.12       0
  5845.0    0.05       0
Bank Sta=5010.6,5021.5
Exp/Cntr=0.3,0.1

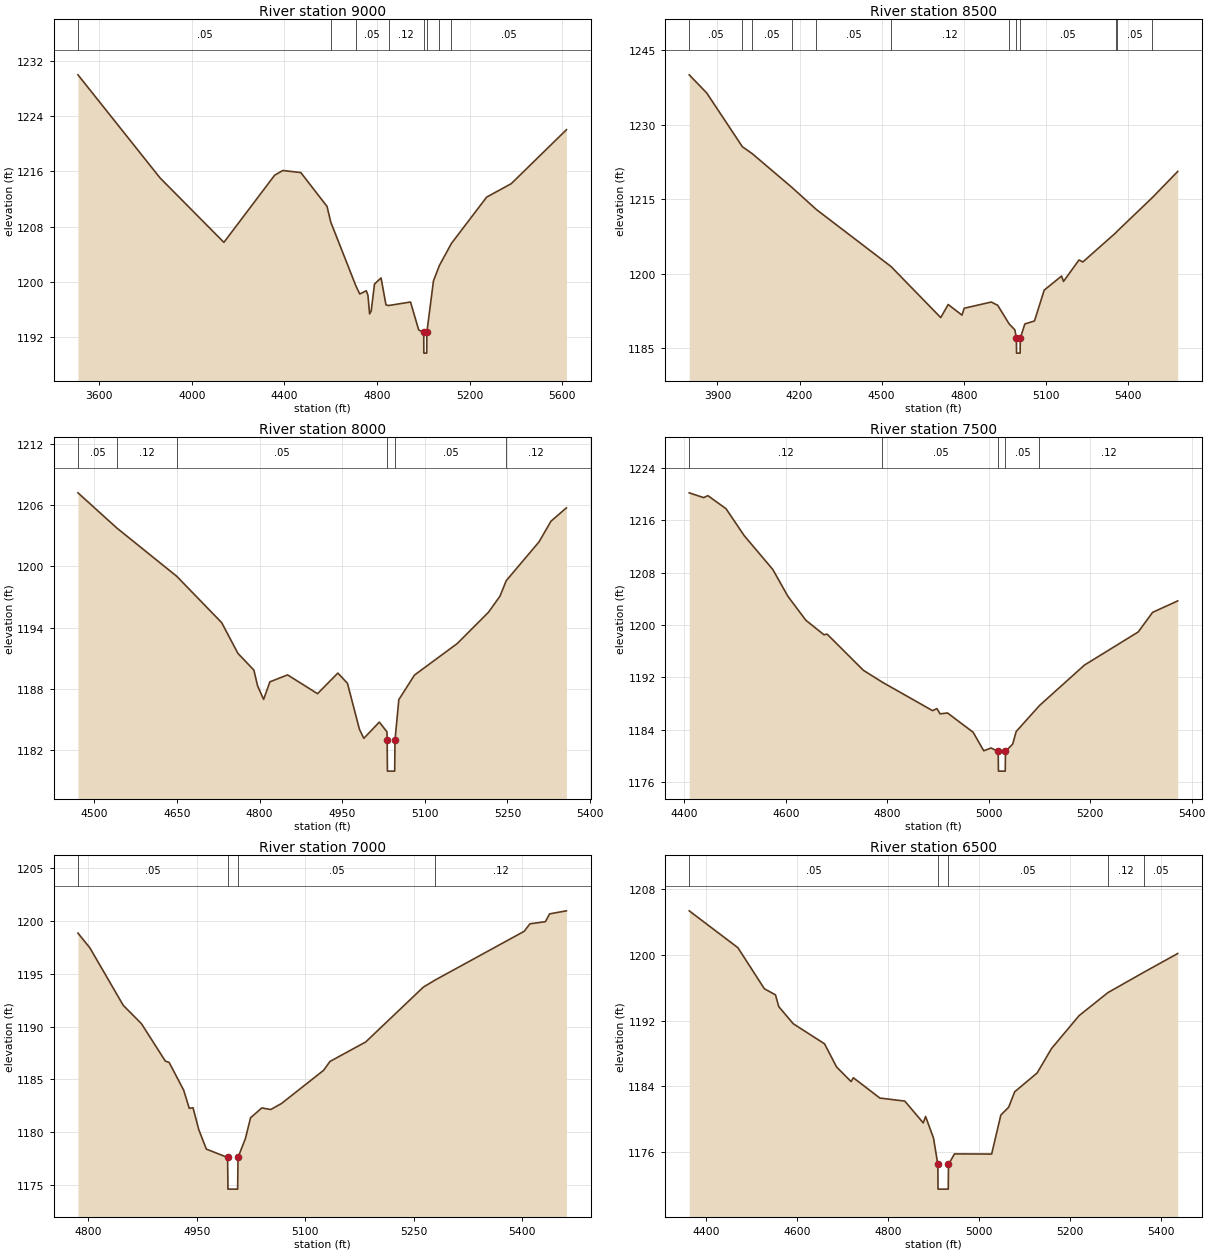
Type RM Length L Ch R = 1,9000,500,500,500
BEGIN DESCRIPTION:
LANG CREEK 18.0
END DESCRIPTION:
XS GIS Cut Line= 3
      2735112.18     10215765.31      2736163.50     10216822.86
      2736660.33     10217191.24
#Sta/Elev= 30
  3508.8 1229.94  3863.3 1215.04  4139.1 1205.72  4358.3 1215.43  4393.6 1216.11
  4471.4 1215.81  4584.5 1210.92  4600.7 1208.65  4709.8 1199.38  4726.0 1198.26
  4754.2 1198.72  4761.3 1198.06  4768.4 1195.38  4775.4 1195.81  4789.6 1199.70
  4817.9 1200.58  4839.1 1196.69  4850.3 1196.59  4945.1 1197.10  4980.5 1193.06
  5002.1 1192.71  5002.6 1189.71  5015.2 1189.71  5015.7 1192.71  5044.3 1200.16
  5070.1 1202.40  5121.9 1205.57  5273.9 1212.26  5380.3 1214.21  5618.5 1222.00
#Mann=8,-1,0
  3508.8    0.05       0  4600.7    0.12       0  4709.8    0.05       0
  4850.3    0.12       0  5002.1    0.07       0  5015.7    0.12       0
  5070.1    0.12       0  5121.9    0.05       0
Bank Sta=5002.1,5015.7
Exp/Cntr=0.3,0.1

Type RM Length L Ch R = 1,8500,500,500,500
BEGIN DESCRIPTION:
LANG CREEK 17.0
END DESCRIPTION:
XS GIS Cut Line= 3
      2734805.66     10216403.09      2735787.35     10217098.42
      2736205.65     10217503.08
#Sta/Elev= 30
  3797.0 1240.09  3861.0 1236.43  3991.3 1225.59  4027.0 1224.21  4172.4 1217.39
  4261.8 1212.93  4534.6 1201.44  4716.1 1191.15  4743.3 1193.79  4793.8 1191.65
  4801.9 1193.04  4900.9 1194.29  4924.3 1193.63  4966.1 1189.88  4987.0 1188.68
  4992.6 1186.99  4993.1 1183.99  5006.3 1183.99  5006.8 1186.99  5023.4 1189.87
  5058.7 1190.48  5094.2 1196.69  5157.7 1199.53  5164.7 1198.44  5221.3 1202.77
  5235.4 1202.37  5357.4 1208.33  5359.5 1208.49  5489.3 1215.34  5582.0 1220.61
#Mann=12,-1,0
  3797.0    0.05       0  3991.3    0.12       0  4027.0    0.05       0
  4172.4    0.12       0  4261.8    0.05       0  4534.6    0.12       0
  4966.1    0.05       0  4992.6    0.03       0  5006.8    0.05       0
  5357.4    0.12       0  5359.5    0.05       0  5489.3    0.12       0
Bank Sta=4992.6,5006.8
Exp/Cntr=0.3,0.1

Type RM Length L Ch R = 1,8000,500,500,500
BEGIN DESCRIPTION:
LANG CREEK 16.0
END DESCRIPTION:
XS GIS Cut Line= 3
      2735155.69     10216853.14      2735363.85     10217340.22
      2735605.68     10217603.11
#Sta/Elev= 30
  4470.3 1207.20  4540.8 1203.76  4649.7 1199.03  4731.3 1194.49  4760.7 1191.49
  4789.7 1189.85  4796.5 1188.30  4807.4 1186.98  4818.8 1188.70  4850.9 1189.38
  4905.3 1187.54  4942.2 1189.56  4959.6 1188.56  4981.4 1184.05  4989.4 1183.17
  5017.5 1184.76  5031.4 1183.80  5031.7 1182.96  5032.2 1179.96  5045.4 1179.96
  5045.9 1182.96  5052.9 1186.96  5081.3 1189.36  5159.0 1192.45  5215.7 1195.51
  5236.7 1197.10  5247.9 1198.60  5307.6 1202.41  5329.1 1204.42  5357.2 1205.73
#Mann=6,-1,0
  4470.3    0.05       0  4540.8    0.12       0  4649.7    0.05       0
  5031.7    0.03       0  5045.9    0.05       0  5247.9    0.12       0
Bank Sta=5031.7,5045.9
Exp/Cntr=0.3,0.1

Type RM Length L Ch R = 1,7500,500,500,500
BEGIN DESCRIPTION:
LANG CREEK 15.0
END DESCRIPTION:
XS GIS Cut Line= 3
      2734455.67     10217253.10      2734937.11     10217595.02
      2735205.70     10217853.12
#Sta/Elev= 30
  4409.5 1220.19  4437.8 1219.46  4446.3 1219.76  4482.1 1217.76  4517.8 1213.66
  4574.3 1208.48  4603.9 1204.40  4639.5 1200.72  4675.2 1198.51  4681.3 1198.61
  4752.9 1193.08  4790.5 1191.25  4889.2 1186.92  4897.9 1187.23  4904.0 1186.43
  4918.8 1186.56  4969.2 1183.62  4990.1 1180.79  5004.7 1181.21  5018.6 1180.68
  5019.1 1177.68  5032.5 1177.68  5033.0 1180.68  5047.2 1181.81  5054.1 1183.73
  5100.0 1187.70  5188.7 1193.88  5294.7 1198.94  5323.0 1201.93  5372.5 1203.68
#Mann=5,-1,0
  4409.5    0.12       0  4790.5    0.05       0  5018.6    0.05       0
  5033.0    0.05       0  5100.0    0.12       0
Bank Sta=5018.6,5033
Exp/Cntr=0.3,0.1

Type RM Length L Ch R = 1,7000,500,500,500
BEGIN DESCRIPTION:
LANG CREEK 14.0
END DESCRIPTION:
XS GIS Cut Line= 3
      2734455.70     10217903.12      2734660.75     10217964.71
      2735055.68     10218203.11
#Sta/Elev= 30
  4785.9 1198.86  4802.4 1197.46  4848.5 1192.02  4873.7 1190.28  4906.7 1186.74
  4912.0 1186.61  4932.1 1183.98  4939.8 1182.26  4945.0 1182.32  4952.9 1180.26
  4963.4 1178.40  4992.8 1177.61  4993.3 1174.61  5006.7 1174.61  5007.2 1177.61
  5017.4 1179.40  5024.6 1181.37  5040.1 1182.30  5052.5 1182.15  5067.3 1182.72
  5125.5 1185.86  5134.3 1186.70  5183.8 1188.55  5263.4 1193.74  5279.9 1194.42
  5402.9 1199.03  5410.8 1199.74  5432.2 1199.94  5438.0 1200.68  5461.3 1200.97
#Mann=4,-1,0
  4785.9    0.05       0  4992.8    0.03       0  5007.2    0.05       0
  5279.9    0.12       0
Bank Sta=4992.8,5007.2
Exp/Cntr=0.3,0.1

Type RM Length L Ch R = 1,6500,500,500,500
BEGIN DESCRIPTION:
LANG CREEK 13.0
END DESCRIPTION:
XS GIS Cut Line= 3
      2734348.28     10217843.07      2734547.93     10218447.65
      2734979.76     10218515.31
#Sta/Elev= 30
  4363.3 1205.38  4470.3 1200.89  4528.5 1195.89  4552.9 1195.15  4560.2 1193.71
  4592.0 1191.63  4660.7 1189.19  4687.2 1186.37  4719.0 1184.59  4724.2 1185.05
  4782.4 1182.58  4837.2 1182.21  4877.7 1179.56  4882.9 1180.34  4900.4 1177.69
  4909.8 1174.49  4910.3 1171.49  4932.7 1171.49  4933.2 1174.49  4946.4 1175.78
  5028.1 1175.76  5048.3 1180.51  5065.5 1181.46  5078.7 1183.34  5128.2 1185.64
  5159.7 1188.61  5220.4 1192.62  5283.7 1195.42  5364.0 1197.94  5437.1 1200.18
#Mann=5,-1,0
  4363.3    0.05       0  4909.8    0.03       0  4933.2    0.05       0
  5283.7    0.12       0  5364.0    0.05       0
Bank Sta=4909.8,4933.2
Exp/Cntr=0.3,0.1

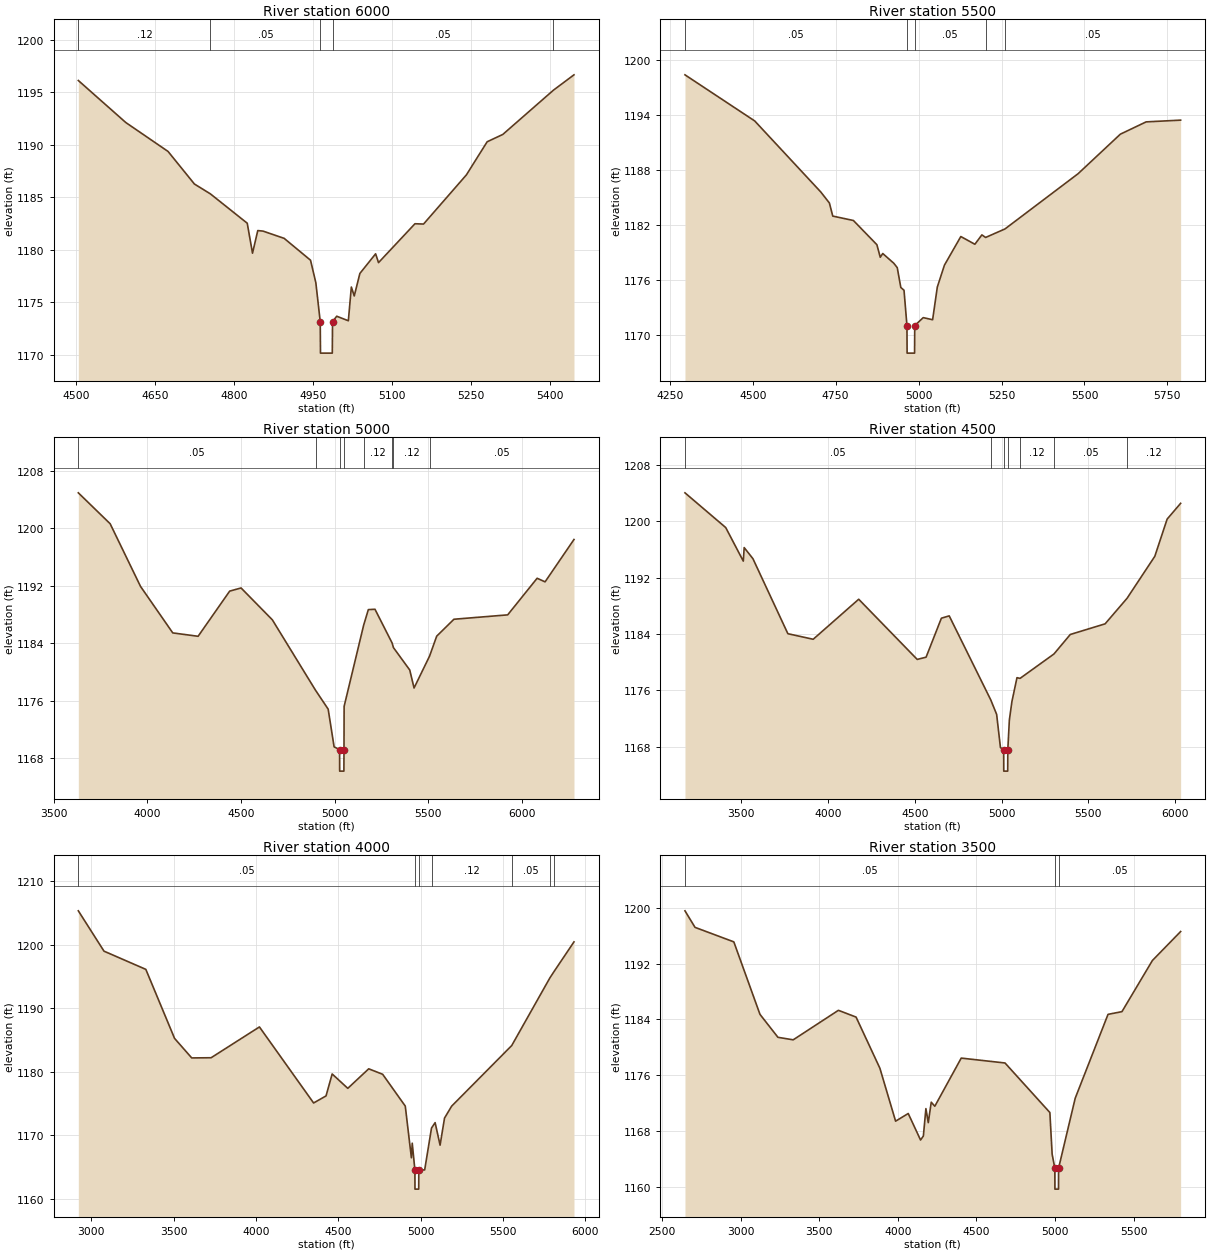
Type RM Length L Ch R = 1,6000,500,500,500
BEGIN DESCRIPTION:
LANG CREEK 12.0
END DESCRIPTION:
XS GIS Cut Line= 3
      2733955.72     10218903.11      2734449.70     10218937.88
      2734855.73     10218753.09
#Sta/Elev= 30
  4504.8 1196.12  4595.0 1192.12  4675.2 1189.37  4725.3 1186.27  4755.7 1185.33
  4825.6 1182.54  4835.6 1179.69  4845.6 1181.84  4855.6 1181.79  4895.7 1181.10
  4945.8 1179.02  4955.9 1176.87  4964.2 1173.18  4964.7 1170.18  4987.1 1170.18
  4987.6 1173.18  4995.5 1173.69  5017.6 1173.26  5023.3 1176.47  5028.8 1175.62
  5039.5 1177.76  5069.4 1179.63  5074.9 1178.79  5144.1 1182.49  5160.4 1182.46
  5241.8 1187.14  5281.2 1190.29  5311.0 1190.99  5407.1 1195.20  5446.1 1196.66
#Mann=5,-1,0
  4504.8    0.12       0  4755.7    0.05       0  4964.2    0.03       0
  4987.6    0.05       0  5407.1    0.12       0
Bank Sta=4964.2,4987.6
Exp/Cntr=0.3,0.1

Type RM Length L Ch R = 1,5500,500,500,500
BEGIN DESCRIPTION:
LANG CREEK 11.0
END DESCRIPTION:
XS GIS Cut Line= 3
      2733900.11     10219544.03      2734588.55     10219395.88
      2735161.92     10218852.56
#Sta/Elev= 30
  4295.8 1198.38  4506.1 1193.35  4704.9 1185.62  4731.1 1184.41  4741.3 1182.98
  4803.5 1182.50  4874.3 1179.86  4884.5 1178.49  4892.0 1178.90  4925.5 1177.83
  4935.7 1177.36  4946.4 1175.20  4956.1 1174.89  4964.9 1171.04  4965.4 1168.04
  4987.9 1168.04  4988.4 1171.04  5014.0 1171.91  5042.3 1171.68  5056.5 1175.25
  5077.9 1177.63  5127.3 1180.75  5169.7 1179.91  5190.8 1180.93  5202.1 1180.65
  5260.5 1181.58  5480.8 1187.60  5608.2 1191.91  5685.9 1193.25  5789.9 1193.44
#Mann=5,-1,0
  4295.8    0.05       0  4964.9    0.03       0  4988.4    0.05       0
  5202.1    0.12       0  5260.5    0.05       0
Bank Sta=4964.9,4988.4
Exp/Cntr=0.3,0.1

Type RM Length L Ch R = 1,5000,500,500,500
BEGIN DESCRIPTION:
LANG CREEK 10.0
END DESCRIPTION:
XS GIS Cut Line= 4
      2733777.89     10219757.90      2734674.22     10219900.50
      2735035.08     10219614.58      2736059.44     10218851.40
#Sta/Elev= 30
  3632.0 1204.91  3801.9 1200.61  3963.9 1191.90  4136.1 1185.43  4271.3 1184.96
  4439.8 1191.24  4500.6 1191.68  4667.5 1187.25  4897.9 1177.46  4965.5 1174.83
  4997.2 1169.58  5026.4 1169.21  5026.9 1166.21  5049.4 1166.21  5049.9 1169.21
  5050.6 1175.21  5154.9 1186.51  5179.9 1188.67  5215.3 1188.72  5306.7 1184.03
  5314.0 1183.38  5400.9 1180.27  5423.9 1177.77  5506.7 1182.21  5544.8 1184.98
  5636.7 1187.33  5923.6 1187.94  6080.7 1193.03  6123.1 1192.53  6277.4 1198.42
#Mann=8,-1,0
  3632.0    0.05       0  4897.9    0.12       0  5026.4    0.07       0
  5049.9    0.12       0  5154.9    0.12       0  5306.7    0.05       0
  5314.0    0.12       0  5506.7    0.05       0
Bank Sta=5026.4,5049.9
Exp/Cntr=0.3,0.1

Type RM Length L Ch R = 1,4500,500,500,500
BEGIN DESCRIPTION:
LANG CREEK 9.0
END DESCRIPTION:
XS GIS Cut Line= 4
      2733665.85     10219849.57      2735051.07     10220134.76
      2735411.82     10219942.63      2736241.72     10219330.88
#Sta/Elev= 30
  3177.0 1204.04  3411.7 1199.11  3512.8 1194.35  3517.9 1196.27  3568.2 1194.70
  3769.5 1184.05  3915.3 1183.26  4177.4 1188.94  4514.3 1180.40  4565.4 1180.72
  4653.4 1186.25  4698.5 1186.58  4938.1 1174.64  4971.6 1172.60  4993.5 1167.90
  5012.1 1167.55  5012.6 1164.55  5035.3 1164.55  5035.8 1167.55  5044.8 1171.79
  5059.4 1174.40  5088.7 1177.81  5106.4 1177.71  5301.5 1181.17  5395.7 1183.94
  5596.2 1185.45  5722.4 1189.07  5882.3 1195.03  5953.3 1200.31  6031.0 1202.55
#Mann=7,-1,0
  3177.0    0.05       0  4938.1    0.12       0  5012.1    0.07       0
  5035.8    0.12       0  5106.4    0.12       0  5301.5    0.05       0
  5722.4    0.12       0
Bank Sta=5012.1,5035.8
Exp/Cntr=0.3,0.1

Type RM Length L Ch R = 1,4000,500,500,500
BEGIN DESCRIPTION:
LANG CREEK 8.0
END DESCRIPTION:
XS GIS Cut Line= 3
      2733605.65     10219903.10      2735627.91     10220380.32
      2736555.70     10220303.11
#Sta/Elev= 30
  2922.2 1205.30  3078.1 1198.96  3332.0 1196.10  3506.4 1185.25  3610.6 1182.18
  3728.3 1182.21  4021.6 1187.05  4350.4 1175.10  4425.9 1176.21  4463.1 1179.66
  4558.0 1177.40  4685.0 1180.47  4769.6 1179.61  4906.9 1174.61  4944.0 1166.49
  4949.2 1168.78  4965.3 1164.56  4965.8 1161.56  4988.5 1161.56  4989.0 1164.56
  5024.7 1164.58  5066.1 1171.15  5088.1 1172.01  5118.2 1168.47  5145.2 1172.73
  5188.4 1174.60  5553.2 1184.13  5785.2 1194.78  5809.5 1195.74  5931.0 1200.42
#Mann=7,-1,0
  2922.2    0.05       0  4965.3    0.03       0  4989.0    0.05       0
  5066.1    0.12       0  5553.2    0.05       0  5785.2    0.12       0
  5809.5    0.05       0
Bank Sta=4965.3,4989
Exp/Cntr=0.3,0.1

Type RM Length L Ch R = 1,3500,1063,1063,1063
BEGIN DESCRIPTION:
LANG CREEK 7.0
END DESCRIPTION:
XS GIS Cut Line= 4
      2733706.66     10219951.44      2735509.41     10220460.69
      2735885.74     10220759.46      2736252.68     10221468.54
#Sta/Elev= 30
  2646.2 1199.57  2710.1 1197.20  2956.9 1195.12  3123.2 1184.73  3237.5 1181.44
  3334.5 1181.08  3622.0 1185.31  3734.3 1184.34  3885.8 1177.01  3985.7 1169.42
  4066.1 1170.52  4144.4 1166.72  4162.3 1167.29  4178.4 1171.22  4193.5 1169.21
  4212.4 1172.14  4235.1 1171.56  4403.1 1178.46  4681.6 1177.76  4966.8 1170.66
  4981.3 1164.68  4998.4 1162.68  4998.9 1159.68  5021.7 1159.68  5022.2 1162.68
  5128.0 1172.71  5336.7 1184.73  5425.3 1185.12  5618.9 1192.45  5798.4 1196.60
#Mann=3,-1,0
  2646.2    0.05       0  4998.4    0.03       0  5022.2    0.05       0
Bank Sta=4998.4,5022.2
Exp/Cntr=0.3,0.1