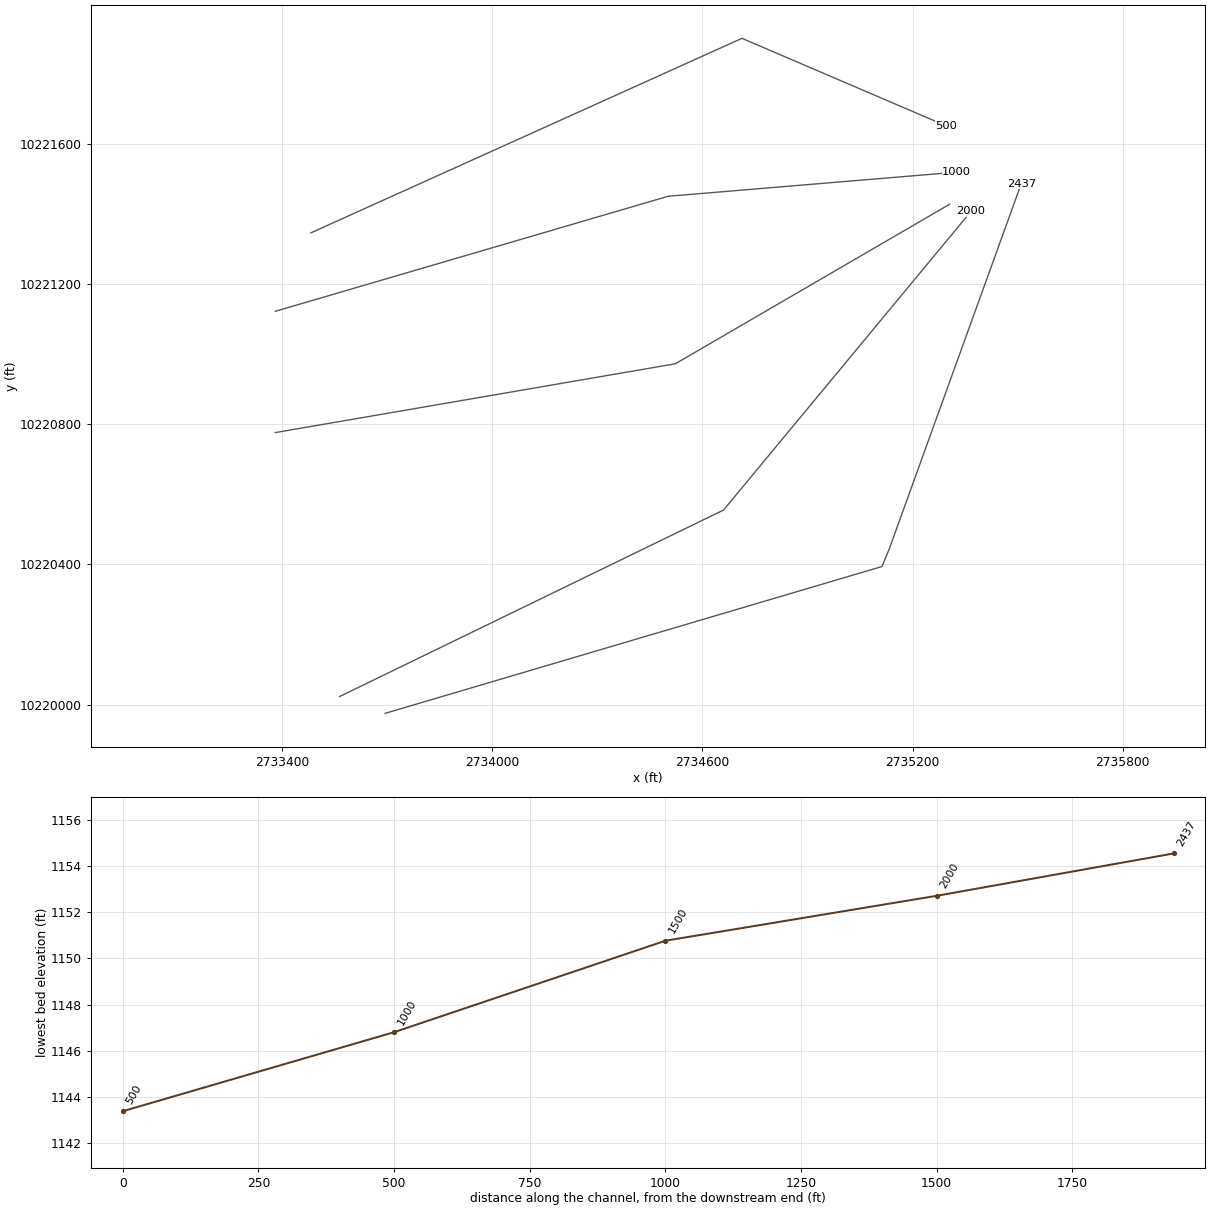
HEC-RAS study LANG CREEK.prj: LANG CREEK Base Level Engineering

--- LANG CREEK.g01 (geometry) --- (continued)

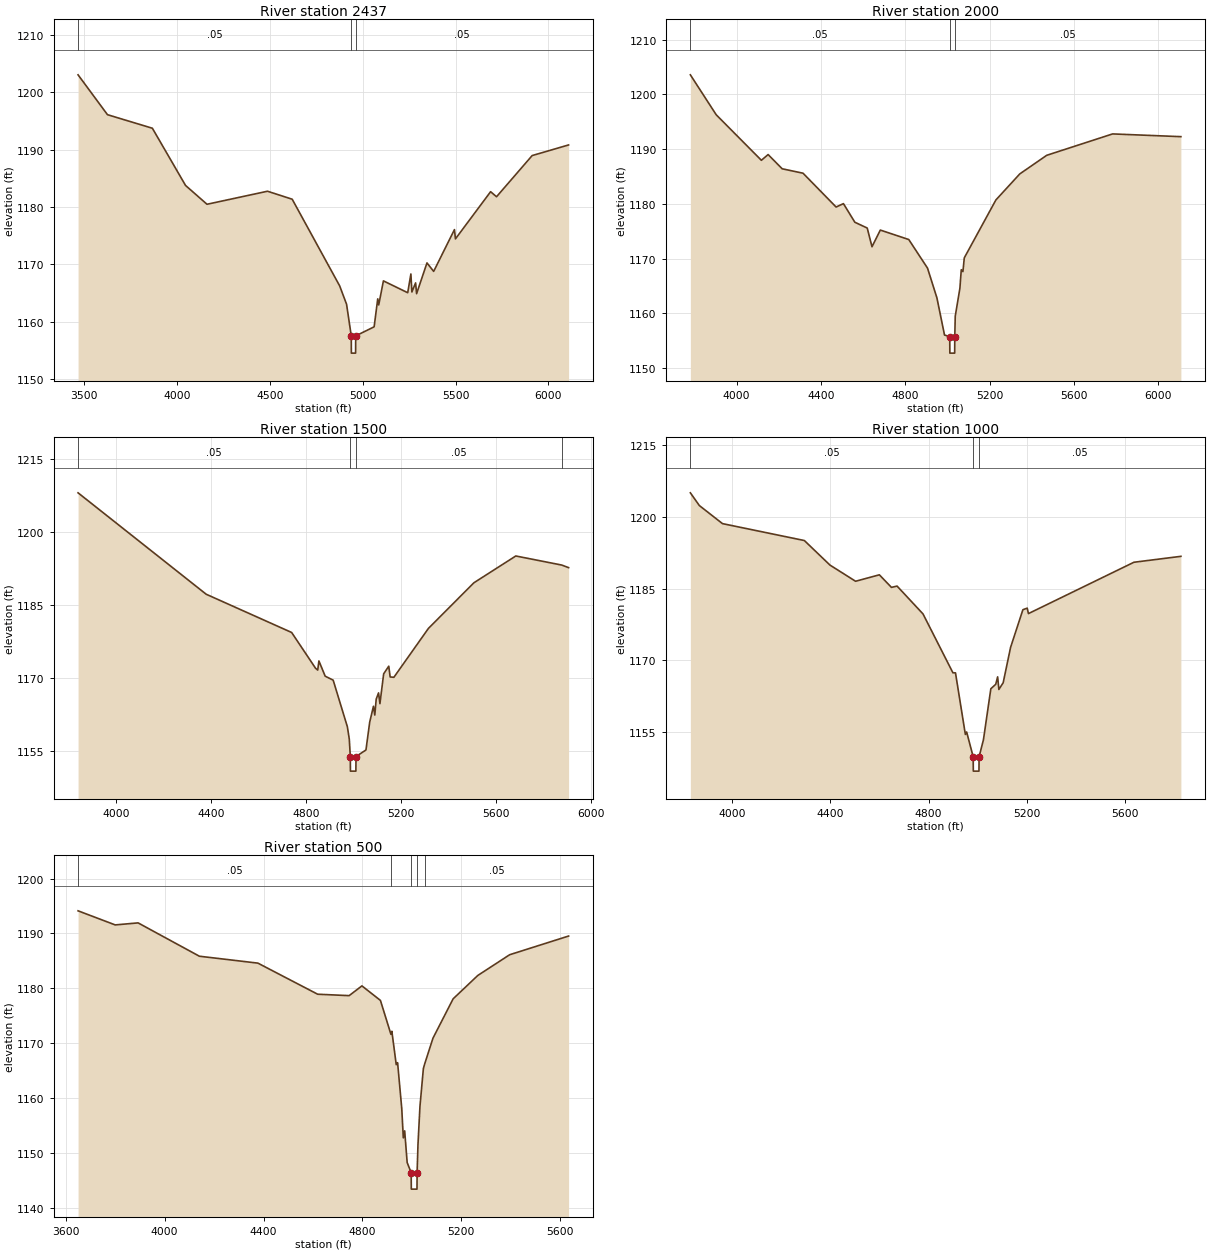
Type RM Length L Ch R = 1,2437,437,437,437
BEGIN DESCRIPTION:
LANG CREEK 5.0
END DESCRIPTION:
XS GIS Cut Line= 4
      2733693.96     10219974.77      2735112.78     10220394.05
      2735133.50     10220444.38      2735510.29     10221487.09
#Sta/Elev= 30
  3466.1 1203.02  3624.5 1196.08  3866.4 1193.72  4045.1 1183.76  4160.7 1180.48
  4486.6 1182.75  4619.7 1181.36  4875.4 1166.27  4912.6 1163.07  4937.9 1157.56
  4938.4 1154.56  4961.3 1154.56  4961.8 1157.56  5061.1 1159.14  5080.5 1164.01
  5085.8 1162.95  5111.1 1167.14  5242.0 1165.08  5259.1 1168.34  5264.5 1165.21
  5284.5 1166.79  5289.8 1164.91  5345.8 1170.27  5381.8 1168.79  5493.8 1176.07
  5499.1 1174.45  5688.6 1182.67  5720.5 1181.79  5912.4 1188.96  6108.7 1190.81
#Mann=3,-1,0
  3466.1    0.05       0  4937.9    0.05       0  4961.8    0.05       0
Bank Sta=4937.9,4961.8
Exp/Cntr=0.3,0.1

Type RM Length L Ch R = 1,2000,500,500,500
BEGIN DESCRIPTION:
LANG CREEK 4.0
END DESCRIPTION:
XS GIS Cut Line= 3
      2733564.06     10220022.73      2734660.35     10220555.28
      2735366.83     10221407.93
#Sta/Elev= 30
  3781.2 1203.58  3903.8 1196.28  4118.0 1187.96  4149.9 1189.01  4216.6 1186.41
  4315.5 1185.60  4472.3 1179.42  4507.1 1180.04  4561.2 1176.64  4619.9 1175.58
  4642.5 1172.16  4682.0 1175.21  4816.9 1173.48  4905.9 1168.25  4950.3 1162.83
  4986.4 1156.03  5011.2 1155.72  5011.7 1152.72  5034.6 1152.72  5035.1 1155.72
  5037.3 1159.46  5059.4 1164.59  5065.9 1167.96  5073.7 1167.62  5080.2 1170.13
  5230.0 1180.71  5343.3 1185.47  5471.0 1188.87  5783.5 1192.78  6107.3 1192.28
#Mann=3,-1,0
  3781.2    0.05       0  5011.2    0.05       0  5035.1    0.05       0
Bank Sta=5011.2,5035.1
Exp/Cntr=0.3,0.1

Type RM Length L Ch R = 1,1500,500,500,500
BEGIN DESCRIPTION:
LANG CREEK 3.0
END DESCRIPTION:
XS GIS Cut Line= 3
      2733380.75     10220776.44      2734522.77     10220972.88
      2735305.58     10221428.21
#Sta/Elev= 30
  3841.2 1208.10  4380.4 1187.21  4740.1 1179.33  4840.6 1171.97  4849.8 1171.59
  4854.8 1173.47  4881.2 1170.33  4914.8 1169.51  4974.7 1159.89  4982.7 1157.35
  4986.9 1153.77  4987.4 1150.77  5010.4 1150.77  5010.9 1153.77  5052.8 1155.13
  5068.5 1160.85  5084.3 1164.13  5090.0 1162.32  5095.9 1165.59  5105.8 1166.89
  5111.6 1164.67  5127.3 1170.81  5148.8 1172.39  5154.6 1170.17  5170.3 1170.10
  5315.7 1180.17  5507.1 1189.57  5683.4 1195.09  5876.8 1193.22  5905.6 1192.69
#Mann=4,-1,0
  3841.2    0.05       0  4986.9    0.03       0  5010.9    0.05       0
  5876.8    0.05       0
Bank Sta=4986.9,5010.9
Exp/Cntr=0.3,0.1

Type RM Length L Ch R = 1,1000,500,500,500
BEGIN DESCRIPTION:
LANG CREEK 2.0
END DESCRIPTION:
XS GIS Cut Line= 3
      2733380.68     10221122.72      2734502.39     10221451.13
      2735326.12     10221519.95
#Sta/Elev= 30
  3831.2 1205.08  3867.7 1202.42  3961.9 1198.63  4294.9 1195.09  4399.1 1189.95
  4503.3 1186.56  4600.0 1187.91  4649.2 1185.28  4672.1 1185.55  4777.6 1179.72
  4899.2 1167.40  4909.7 1167.38  4949.9 1154.48  4955.1 1155.00  4981.7 1149.80
  4982.2 1146.80  5005.2 1146.80  5005.7 1149.80  5023.4 1153.36  5053.5 1164.05
  5073.5 1164.99  5081.2 1166.54  5086.2 1163.90  5103.7 1165.31  5133.8 1172.71
  5183.9 1180.60  5201.5 1180.93  5206.5 1179.79  5635.5 1190.54  5826.6 1191.78
#Mann=3,-1,0
  3831.2    0.05       0  4981.7    0.05       0  5005.7    0.05       0
Bank Sta=4981.7,5005.7
Exp/Cntr=0.3,0.1

Type RM Length L Ch R = 1,500,0,0,0
BEGIN DESCRIPTION:
LANG CREEK 1.0
END DESCRIPTION:
XS GIS Cut Line= 3
      2733482.53     10221346.79      2734712.96     10221902.01
      2735295.52     10221652.35
#Sta/Elev= 30
  3650.1 1194.13  3800.4 1191.56  3892.9 1191.93  4140.7 1185.85  4377.4 1184.59
  4619.0 1178.92  4746.3 1178.66  4798.0 1180.44  4872.9 1177.79  4915.4 1171.60
  4919.1 1172.16  4936.8 1166.07  4942.3 1166.43  4959.1 1158.08  4965.4 1152.72
  4970.9 1154.00  4981.0 1148.21  4997.2 1146.37  4997.7 1143.37  5020.7 1143.37
  5021.2 1146.37  5024.7 1151.50  5032.7 1158.45  5046.5 1165.35  5051.3 1166.13
  5085.3 1170.90  5166.9 1178.08  5266.6 1182.34  5395.4 1186.12  5633.8 1189.53
#Mann=5,-1,0
  3650.1    0.05       0  4915.4    0.12       0  4997.2    0.07       0
  5021.2    0.12       0  5051.3    0.05       0
Bank Sta=4997.2,5021.2
Exp/Cntr=0.3,0.1

Chan Stop Cuts=-1