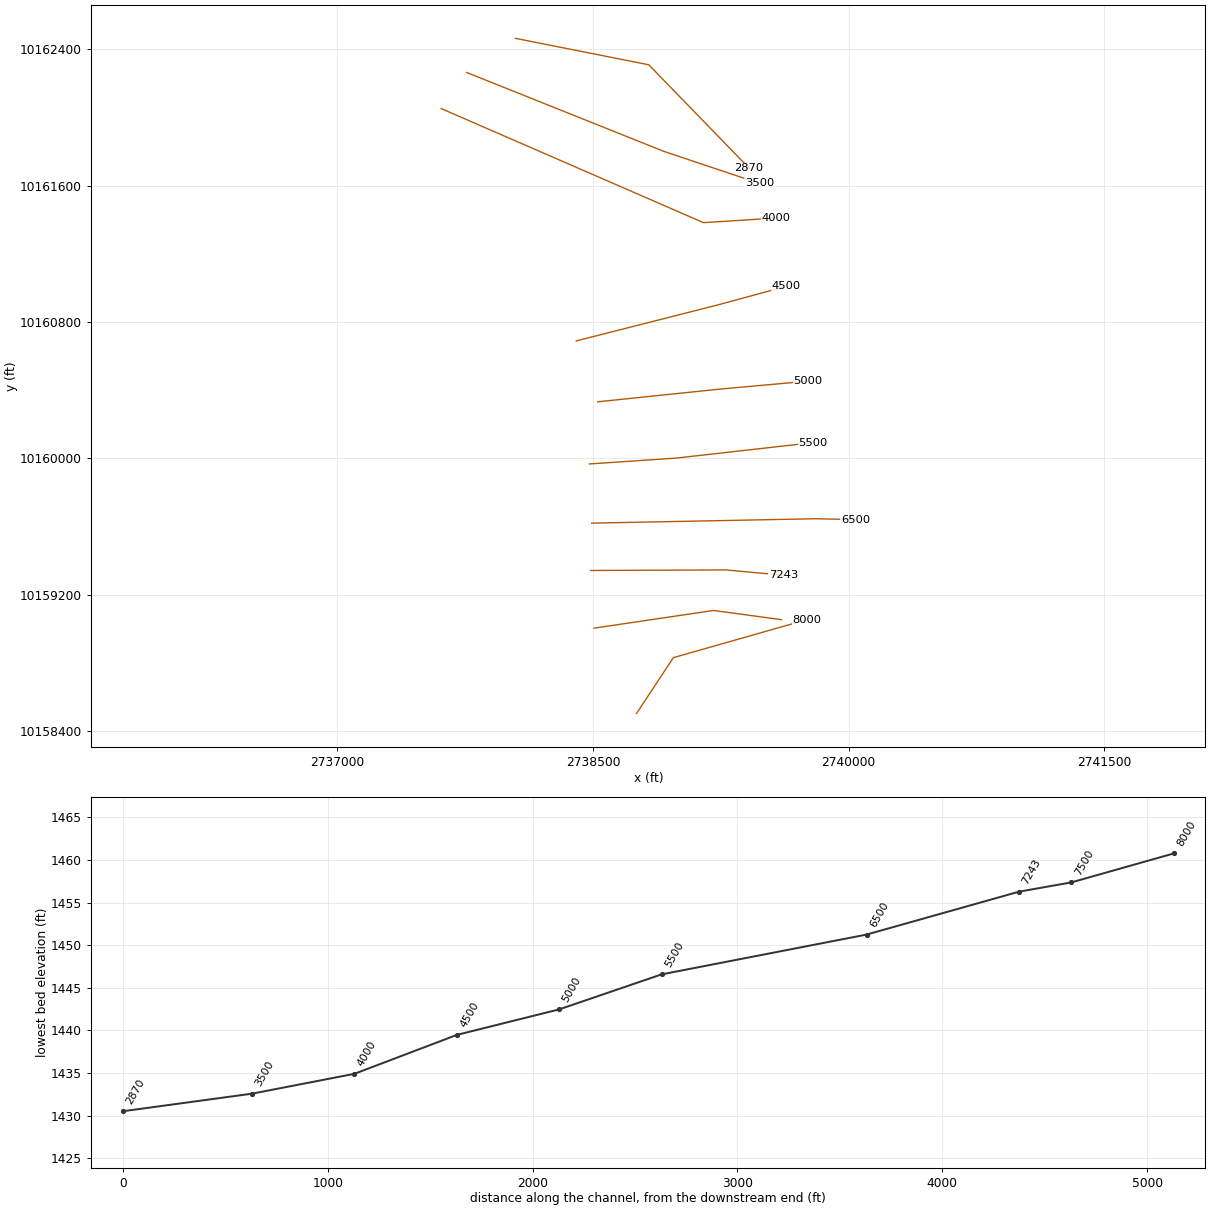
HEC-RAS study LITTLE COTTONWOOD CREEK.prj: LITTLE COTTONWOOD CREEK Base Level Engineering

--- LITTLE COTTONWOOD CREEK.g01 (geometry) --- (continued)

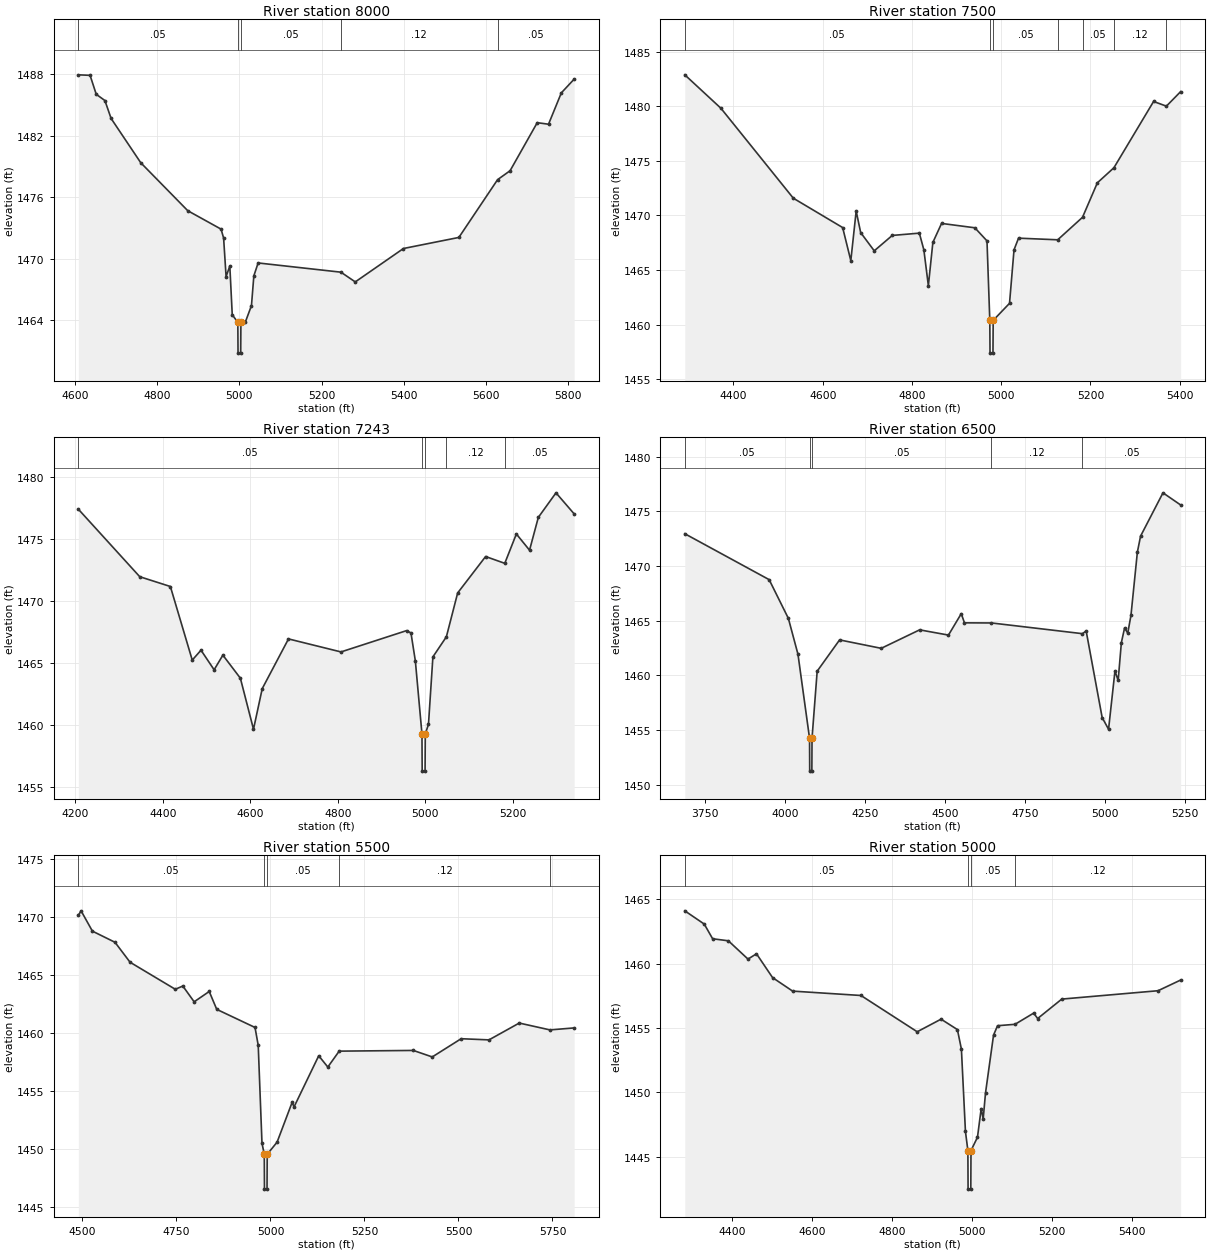
Type RM Length L Ch R = 1,8000,500,500,500
BEGIN DESCRIPTION:
LITTLE COTTONWOOD CREEK 16.0
END DESCRIPTION:
XS GIS Cut Line= 3
      2738755.69     10158503.12      2738971.69     10158830.24
      2739755.72     10159053.12
#Sta/Elev= 30
  4608.0 1487.94  4636.6 1487.89  4651.6 1486.04  4672.7 1485.43  4687.8 1483.68
  4760.0 1479.36  4874.4 1474.68  4955.5 1472.88  4961.7 1472.01  4967.7 1468.25
  4976.8 1469.28  4982.7 1464.53  4996.3 1463.78  4996.8 1460.78  5003.3 1460.78
  5003.8 1463.78  5014.5 1463.80  5029.5 1465.42  5035.3 1468.32  5045.7 1469.58
  5247.3 1468.68  5282.2 1467.73  5399.5 1470.99  5534.4 1472.07  5628.7 1477.71
  5659.1 1478.58  5725.2 1483.27  5752.7 1483.12  5783.9 1486.18  5815.1 1487.52
#Mann=5,-1,0
  4608.0    0.05       0  4996.3    0.03       0  5003.8    0.05       0
  5247.3    0.12       0  5628.7    0.05       0
Bank Sta=4996.3,5003.8
Exp/Cntr=0.3,0.1

Type RM Length L Ch R = 1,7500,257,257,257
BEGIN DESCRIPTION:
LITTLE COTTONWOOD CREEK 15.0
END DESCRIPTION:
XS GIS Cut Line= 3
      2738505.70     10159003.11      2739207.14     10159107.04
      2739605.71     10159053.11
#Sta/Elev= 30
  4290.9 1482.87  4371.8 1479.81  4534.1 1471.57  4644.7 1468.88  4663.0 1465.85
  4675.0 1470.39  4685.1 1468.42  4715.5 1466.75  4755.9 1468.16  4816.6 1468.37
  4826.7 1466.84  4836.8 1463.56  4846.9 1467.52  4866.4 1469.26  4941.0 1468.86
  4968.2 1467.66  4974.5 1460.38  4975.0 1457.38  4981.6 1457.38  4982.1 1460.38
  5018.7 1461.94  5028.8 1466.84  5038.9 1467.91  5126.7 1467.76  5182.3 1469.82
  5215.6 1472.98  5252.7 1474.36  5341.6 1480.43  5370.3 1480.00  5402.2 1481.33
#Mann=7,-1,0
  4290.9    0.05       0  4974.5    0.05       0  4982.1    0.05       0
  5126.7    0.12       0  5182.3    0.05       0  5252.7    0.12       0
  5370.3    0.05       0
Bank Sta=4974.5,4982.1
Exp/Cntr=0.3,0.1

Type RM Length L Ch R = 1,7243,743,743,743
BEGIN DESCRIPTION:
LITTLE COTTONWOOD CREEK 14.0
END DESCRIPTION:
XS GIS Cut Line= 3
      2738485.31     10159341.65      2739278.50     10159345.00
      2739617.27     10159313.88
#Sta/Elev= 30
  4206.8 1477.42  4347.2 1471.97  4417.2 1471.18  4467.2 1465.24  4487.2 1466.04
  4517.2 1464.46  4537.2 1465.64  4577.2 1463.78  4607.2 1459.66  4627.2 1462.94
  4687.2 1466.95  4807.2 1465.90  4957.2 1467.62  4967.2 1467.43  4977.2 1465.17
  4992.3 1459.28  4992.8 1456.28  4999.4 1456.28  4999.9 1459.28  5007.2 1460.06
  5017.3 1465.50  5048.1 1467.12  5073.9 1470.66  5137.8 1473.60  5181.6 1473.05
  5208.1 1475.42  5238.2 1474.11  5258.3 1476.76  5298.7 1478.74  5340.2 1477.04
#Mann=5,-1,0
  4206.8    0.05       0  4992.3    0.05       0  4999.9    0.05       0
  5048.1    0.12       0  5181.6    0.05       0
Bank Sta=4992.3,4999.9
Exp/Cntr=0.3,0.1

Type RM Length L Ch R = 1,6500,1000,1000,1000
BEGIN DESCRIPTION:
LITTLE COTTONWOOD CREEK 13.0
END DESCRIPTION:
XS GIS Cut Line= 3
      2738492.24     10159619.43      2739804.79     10159645.23
      2740040.74     10159640.27
#Sta/Elev= 30
  3687.2 1472.96  3950.7 1468.76  4010.7 1465.22  4040.7 1461.94  4076.9 1454.25
  4077.4 1451.25  4084.1 1451.25  4084.6 1454.25  4100.7 1460.39  4170.7 1463.25
  4300.8 1462.48  4420.8 1464.17  4510.8 1463.69  4550.8 1465.65  4560.8 1464.81
  4645.2 1464.80  4929.3 1463.82  4940.9 1464.07  4990.9 1456.15  5010.9 1455.08
  5030.9 1460.41  5040.9 1459.54  5050.9 1463.00  5060.9 1464.34  5070.9 1463.87
  5080.9 1465.50  5100.9 1471.28  5110.9 1472.74  5180.9 1476.70  5236.0 1475.59
#Mann=5,-1,0
  3687.2    0.05       0  4076.9    0.03       0  4084.6    0.05       0
  4645.2    0.12       0  4929.3    0.05       0
Bank Sta=4076.9,4084.6
Exp/Cntr=0.3,0.1

Type RM Length L Ch R = 1,5500,500,500,500
BEGIN DESCRIPTION:
LITTLE COTTONWOOD CREEK 11.0
END DESCRIPTION:
XS GIS Cut Line= 3
      2738478.39     10159966.66      2738988.23     10160001.12
      2739790.74     10160091.64
#Sta/Elev= 30
  4489.0 1470.17  4496.3 1470.56  4526.4 1468.81  4586.5 1467.85  4626.6 1466.13
  4746.9 1463.80  4766.9 1464.08  4797.0 1462.72  4837.1 1463.61  4857.1 1462.07
  4958.9 1460.51  4967.4 1458.97  4977.4 1450.54  4983.5 1449.58  4984.0 1446.58
  4990.8 1446.58  4991.3 1449.58  5017.6 1450.63  5057.6 1454.06  5062.6 1453.66
  5128.3 1458.07  5152.5 1457.10  5182.7 1458.47  5379.9 1458.53  5430.2 1457.97
  5507.1 1459.54  5581.1 1459.44  5661.6 1460.89  5743.2 1460.30  5807.6 1460.47
#Mann=5,-1,0
  4489.0    0.05       0  4983.5    0.05       0  4991.3    0.05       0
  5182.7    0.12       0  5743.2    0.05       0
Bank Sta=4983.5,4991.3
Exp/Cntr=0.3,0.1

Type RM Length L Ch R = 1,5000,500,500,500
BEGIN DESCRIPTION:
LITTLE COTTONWOOD CREEK 10.0
END DESCRIPTION:
XS GIS Cut Line= 3
      2738527.29     10160331.35      2739241.34     10160405.59
      2739761.91     10160452.66
#Sta/Elev= 30
  4282.1 1464.10  4330.8 1463.07  4351.7 1461.93  4391.1 1461.77  4440.2 1460.35
  4461.5 1460.76  4501.7 1458.91  4551.9 1457.86  4722.9 1457.52  4863.6 1454.70
  4923.3 1455.68  4964.2 1454.87  4974.2 1453.35  4984.3 1446.95  4990.4 1445.47
  4990.9 1442.47  4997.7 1442.47  4998.2 1445.47  5014.4 1446.50  5023.7 1448.73
  5028.7 1447.93  5034.5 1449.94  5054.6 1454.44  5064.6 1455.17  5108.3 1455.28
  5155.0 1456.15  5165.0 1455.73  5225.3 1457.24  5466.2 1457.89  5522.7 1458.72
#Mann=4,-1,0
  4282.1    0.05       0  4990.4    0.05       0  4998.2    0.05       0
  5108.3    0.12       0
Bank Sta=4990.4,4998.2
Exp/Cntr=0.3,0.1

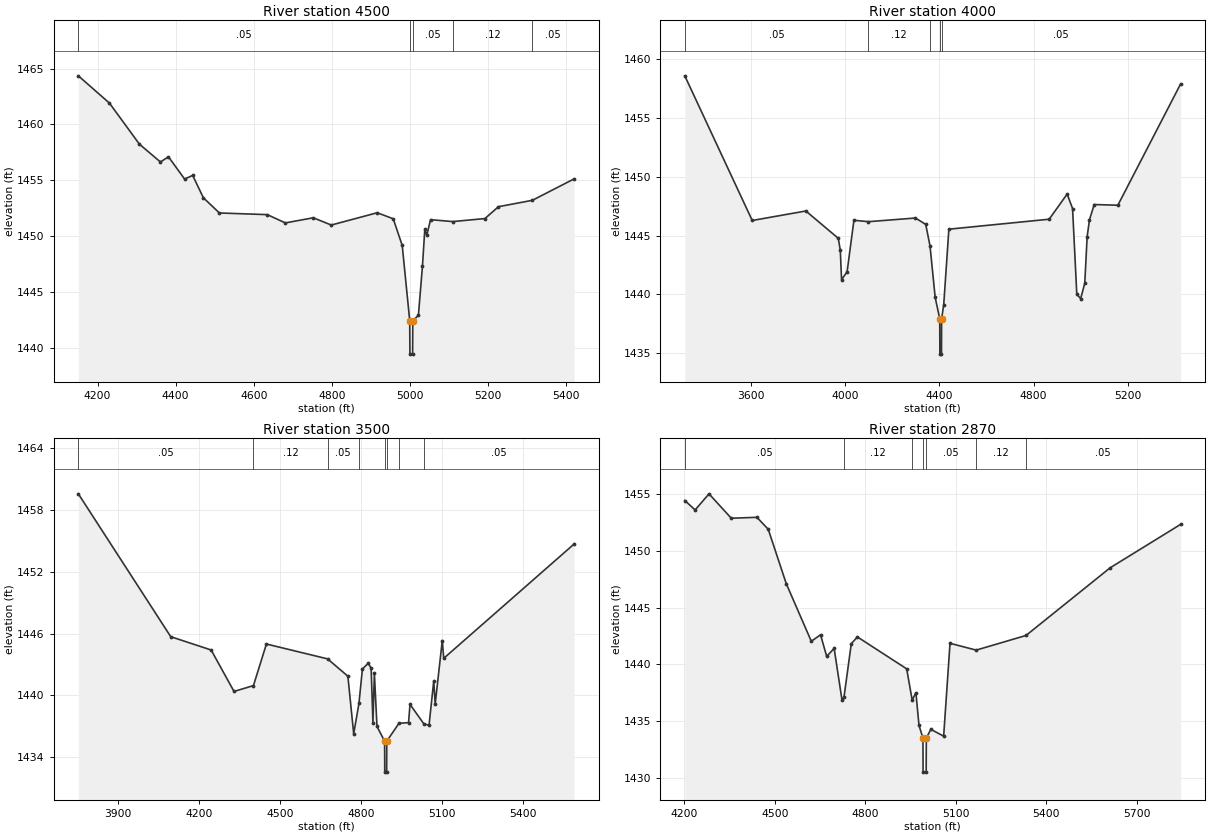
Type RM Length L Ch R = 1,4500,500,500,500
BEGIN DESCRIPTION:
LITTLE COTTONWOOD CREEK 9.0
END DESCRIPTION:
XS GIS Cut Line= 3
      2738401.98     10160688.88      2739224.93     10160897.98
      2739630.53     10161008.15
#Sta/Elev= 30
  4150.9 1464.35  4230.6 1461.91  4307.3 1458.24  4361.1 1456.65  4381.7 1457.11
  4423.0 1455.12  4443.6 1455.45  4471.0 1453.45  4512.0 1452.09  4634.8 1451.94
  4680.9 1451.20  4752.4 1451.66  4798.5 1451.01  4916.2 1452.11  4957.1 1451.57
  4980.1 1449.19  4999.3 1442.47  4999.8 1439.47  5006.7 1439.47  5007.2 1442.47
  5021.5 1442.93  5031.9 1447.33  5037.9 1450.62  5043.0 1450.10  5052.6 1451.49
  5109.5 1451.32  5191.9 1451.59  5226.5 1452.65  5313.2 1453.22  5420.3 1455.14
#Mann=5,-1,0
  4150.9    0.05       0  4999.3    0.05       0  5007.2    0.05       0
  5109.5    0.12       0  5313.2    0.05       0
Bank Sta=4999.3,5007.2
Exp/Cntr=0.3,0.1

Type RM Length L Ch R = 1,4000,500,500,500
BEGIN DESCRIPTION:
LITTLE COTTONWOOD CREEK 8.0
END DESCRIPTION:
XS GIS Cut Line= 3
      2737608.61     10162052.29      2739148.32     10161382.71
      2739571.38     10161409.41
#Sta/Elev= 30
  3321.0 1458.60  3607.0 1446.28  3834.4 1447.09  3972.1 1444.76  3980.5 1443.74
  3985.9 1441.24  4009.4 1441.92  4038.3 1446.30  4099.9 1446.18  4299.2 1446.49
  4342.8 1445.95  4361.1 1444.11  4382.8 1439.75  4402.3 1437.90  4402.8 1434.90
  4409.7 1434.90  4410.2 1437.90  4419.2 1439.12  4441.0 1445.54  4866.4 1446.39
  4942.6 1448.53  4965.6 1447.30  4983.6 1439.99  5000.0 1439.63  5017.4 1440.94
  5027.4 1444.90  5037.4 1446.35  5057.5 1447.64  5157.7 1447.58  5423.9 1457.91
#Mann=5,-1,0
  3321.0    0.05       0  4099.9    0.12       0  4361.1    0.05       0
  4402.3    0.05       0  4410.2    0.05       0
Bank Sta=4402.3,4410.2
Exp/Cntr=0.3,0.1

Type RM Length L Ch R = 1,3500,630,630,630
BEGIN DESCRIPTION:
LITTLE COTTONWOOD CREEK 7.0
END DESCRIPTION:
XS GIS Cut Line= 3
      2737759.19     10162263.66      2738915.77     10161800.95
      2739475.11     10161613.55
#Sta/Elev= 30
  3754.3 1459.55  4096.4 1445.70  4246.0 1444.41  4330.7 1440.39  4402.6 1440.96
  4450.6 1444.99  4676.9 1443.55  4752.2 1441.87  4773.7 1436.28  4793.2 1439.23
  4806.0 1442.57  4827.6 1443.13  4838.3 1442.64  4844.9 1437.38  4850.3 1442.16
  4859.9 1437.00  4888.2 1435.57  4888.7 1432.57  4895.7 1432.57  4896.2 1435.57
  4941.2 1437.30  4976.8 1437.37  4982.2 1439.14  5032.6 1437.28  5052.6 1437.10
  5070.2 1441.44  5075.4 1439.16  5101.7 1445.33  5107.0 1443.60  5589.9 1454.69
#Mann=8,-1,0
  3754.3    0.05       0  4402.6    0.12       0  4676.9    0.05       0
  4793.2    0.12       0  4888.2    0.07       0  4896.2    0.12       0
  4941.2    0.12       0  5032.6    0.05       0
Bank Sta=4888.2,4896.2
Exp/Cntr=0.3,0.1

Type RM Length L Ch R = 1,2870,0,0,0
BEGIN DESCRIPTION:
LITTLE COTTONWOOD CREEK 6.0
END DESCRIPTION:
XS GIS Cut Line= 3
      2738044.60     10162464.25      2738827.25     10162309.00
      2739415.63     10161702.78
#Sta/Elev= 30
  4202.1 1454.44  4236.3 1453.61  4282.3 1455.03  4356.1 1452.88  4441.0 1452.96
  4478.5 1451.91  4538.3 1447.11  4621.2 1442.04  4651.8 1442.61  4672.2 1440.71
  4696.9 1441.41  4723.1 1436.83  4729.5 1437.11  4753.7 1441.83  4774.1 1442.42
  4937.2 1439.61  4955.4 1436.86  4967.8 1437.51  4978.0 1434.63  4991.1 1433.51
  4991.6 1430.51  5001.8 1430.51  5002.3 1433.51  5017.2 1434.28  5059.7 1433.68
  5080.8 1441.86  5167.5 1441.26  5332.5 1442.55  5611.2 1448.51  5844.8 1452.34
#Mann=7,-1,0
  4202.1    0.05       0  4729.5    0.12       0  4955.4    0.05       0
  4991.1    0.05       0  5002.3    0.05       0  5167.5    0.12       0
  5332.5    0.05       0
Bank Sta=4991.1,5002.3
Exp/Cntr=0.3,0.1

Chan Stop Cuts=-1