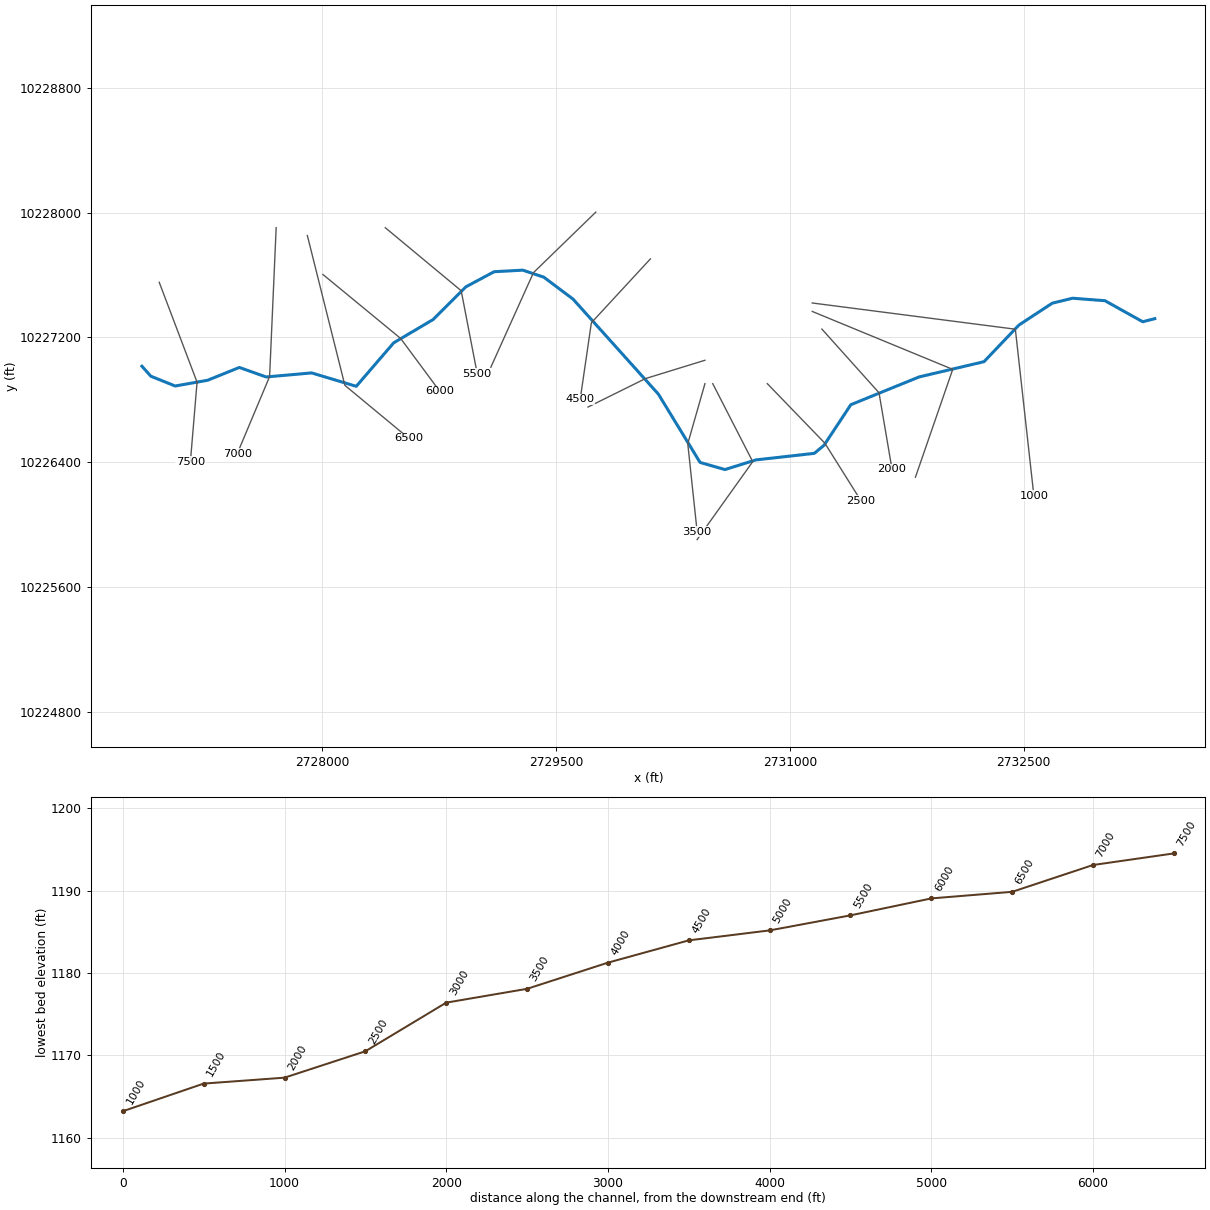
--- SAND CREEK.prj (project) ---

Proj Title=SAND CREEK Base Level Engineering
Current Plan=p01
Default Exp/Contr=0.3,0.1
English Units
Geom File=g01
Flow File=f01
Plan File=p01
BEGIN DESCRIPTION:
SAND CREEK
END DESCRIPTION:

--- SAND CREEK.p01 (plan) ---

Plan Title=Multiple Run
Short Identifier=Multiple
Geom File=g01
Flow File=f01
Subcritical Flow
K Sum by GR= 0
Std Step Tol= 0.01
Critical Tol= 0.01
Num of Std Step Trials= 20
Max Error Tol= 0.3
Flow Tol Ratio= 0.001
Split Flow NTrial= 30
Split Flow Tol= 0.02
Split Flow Ratio= 0.02
Log Output Level= 0
Friction Slope Method= 1
Unsteady Friction Slope Method= 2
Unsteady Bridges Friction Slope Method= 1
Parabolic Critical Depth
Global Vel Dist=  1 , 1 , 1
Global Log Level= 0
CheckData=True
Encroach Param= -1, 0, 0, 0
BEGIN DESCRIPTION:
Multiple Run
END DESCRIPTION:

--- SAND CREEK.f01 (steady flow) ---

Flow Title=Multiple
Number of Profiles=7
Profile Names=10-year,25-year,50-year,1pct_min,100-year,1pct_plu,500-year
River Rch & RM= SAND CREEK,Reach-1,7500
     198     436     725     395    1194    3606    3438
Boundary for River Rch & Prof#=SAND CREEK,Reach-1,1
Up Type=0
Dn Type=3
Dn Slope=0.005
Boundary for River Rch & Prof#=SAND CREEK,Reach-1,2
Up Type=0
Dn Type=3
Dn Slope=0.005
Boundary for River Rch & Prof#=SAND CREEK,Reach-1,3
Up Type=0
Dn Type=3
Dn Slope=0.005
Boundary for River Rch & Prof#=SAND CREEK,Reach-1,4
Up Type=0
Dn Type=3
Dn Slope=0.005
Boundary for River Rch & Prof#=SAND CREEK,Reach-1,5
Up Type=0
Dn Type=3
Dn Slope=0.005
Boundary for River Rch & Prof#=SAND CREEK,Reach-1,6
Up Type=0
Dn Type=3
Dn Slope=0.005
Boundary for River Rch & Prof#=SAND CREEK,Reach-1,7
Up Type=0
Dn Type=3
Dn Slope=0.005

--- SAND CREEK.g01 (geometry) ---

Geom Title=Existing Conditions

River Reach=SAND CREEK,Reach-1
Reach XY= 30
      2726844.75     10227015.00      2726901.75     10226951.00
      2727058.00     10226888.00      2727266.25     10226925.00
      2727469.50     10227007.00      2727641.25     10226946.00
      2727933.00     10226972.00      2728219.25     10226886.00
      2728459.50     10227165.00      2728711.75     10227314.00
      2728922.50     10227524.00      2729103.50     10227621.00
      2729287.00     10227631.00      2729422.25     10227586.00
      2729610.00     10227445.00      2730157.00     10226836.00
      2730424.25     10226398.00      2730584.00     10226352.00
      2730782.00     10226414.00      2731157.00     10226456.00
      2731219.50     10226508.00      2731391.25     10226768.00
      2731828.75     10226946.00      2732245.50     10227044.00
      2732469.50     10227279.00      2732683.00     10227419.00
      2732813.25     10227451.00      2733021.50     10227435.00
      2733263.75     10227300.00      2733340.75     10227320.00

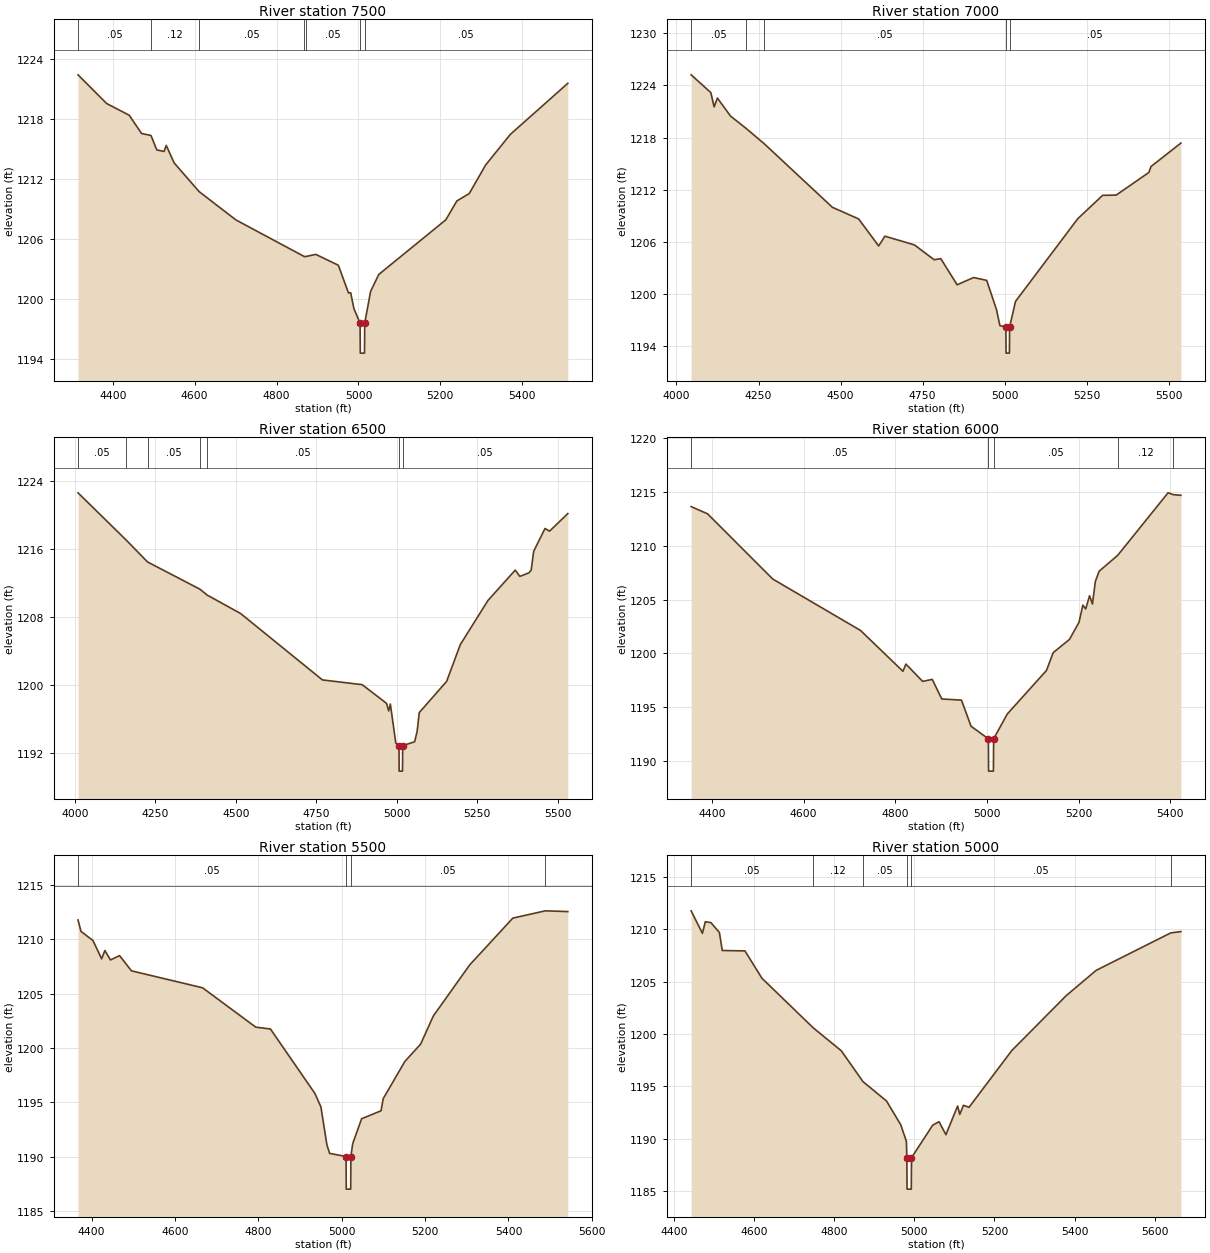
Type RM Length L Ch R = 1,7500,500,500,500
BEGIN DESCRIPTION:
SAND CREEK 15.0
END DESCRIPTION:
XS GIS Cut Line= 3
      2726955.70     10227553.08      2727198.28     10226912.68
      2727155.69     10226403.16
#Sta/Elev= 30
  4315.2 1222.44  4385.2 1219.56  4440.2 1218.39  4470.3 1216.56  4493.4 1216.36
  4507.6 1214.91  4525.3 1214.76  4530.6 1215.36  4550.1 1213.60  4611.0 1210.73
  4700.9 1207.89  4867.4 1204.23  4870.9 1204.22  4895.9 1204.44  4950.9 1203.35
  4975.7 1200.57  4981.0 1200.60  4988.8 1199.02  5004.0 1197.54  5004.5 1194.54
  5014.8 1194.54  5015.3 1197.54  5029.7 1200.73  5049.7 1202.43  5213.3 1207.90
  5240.4 1209.80  5270.5 1210.53  5310.6 1213.40  5370.9 1216.47  5511.3 1221.59
#Mann=7,-1,0
  4315.2    0.05       0  4493.4    0.12       0  4611.0    0.05       0
  4867.4    0.12       0  4870.9    0.05       0  5004.0    0.03       0
  5015.3    0.05       0
Bank Sta=5004,5015.3
Exp/Cntr=0.3,0.1

Type RM Length L Ch R = 1,7000,500,500,500
BEGIN DESCRIPTION:
SAND CREEK 14.0
END DESCRIPTION:
XS GIS Cut Line= 3
      2727705.69     10227903.15      2727663.61     10226948.68
      2727455.69     10226453.13
#Sta/Elev= 30
  4044.6 1225.23  4104.7 1223.18  4114.7 1221.53  4124.7 1222.55  4164.8 1220.47
  4212.2 1219.05  4268.0 1217.26  4475.1 1209.95  4555.1 1208.61  4616.2 1205.49
  4635.2 1206.62  4725.3 1205.61  4785.4 1203.90  4805.4 1204.03  4855.4 1201.01
  4905.5 1201.85  4945.5 1201.52  4975.5 1198.12  4985.6 1196.31  5003.9 1196.13
  5004.4 1193.13  5014.7 1193.13  5015.2 1196.13  5033.3 1199.10  5222.9 1208.63
  5298.8 1211.33  5340.2 1211.36  5439.8 1213.97  5446.1 1214.65  5537.4 1217.36
#Mann=5,-1,0
  4044.6    0.05       0  4212.2    0.12       0  4268.0    0.05       0
  5003.9    0.03       0  5015.2    0.05       0
Bank Sta=5003.9,5015.2
Exp/Cntr=0.3,0.1

Type RM Length L Ch R = 1,6500,500,500,500
BEGIN DESCRIPTION:
SAND CREEK 13.0
END DESCRIPTION:
XS GIS Cut Line= 3
      2727905.68     10227853.14      2728146.41     10226892.24
      2728555.67     10226553.12
#Sta/Elev= 30
  4009.4 1222.64  4159.3 1217.07  4225.4 1214.50  4387.8 1211.30  4411.2 1210.59
  4514.6 1208.43  4768.9 1200.61  4892.5 1200.05  4968.2 1197.85  4974.9 1196.96
  4980.0 1197.77  4997.0 1193.16  5006.8 1192.87  5007.3 1189.87  5017.8 1189.87
  5018.3 1192.87  5055.5 1193.33  5063.3 1194.57  5069.8 1196.76  5154.9 1200.44
  5197.4 1204.77  5283.4 1209.97  5368.1 1213.54  5382.4 1212.80  5411.1 1213.23
  5417.6 1213.54  5425.4 1215.75  5460.5 1218.44  5474.9 1218.13  5531.5 1220.20
#Mann=7,-1,0
  4009.4    0.05       0  4159.3    0.12       0  4225.4    0.05       0
  4387.8    0.12       0  4411.2    0.05       0  5006.8    0.03       0
  5018.3    0.05       0
Bank Sta=5006.8,5018.3
Exp/Cntr=0.3,0.1

Type RM Length L Ch R = 1,6000,500,500,500
BEGIN DESCRIPTION:
SAND CREEK 12.0
END DESCRIPTION:
XS GIS Cut Line= 3
      2728005.68     10227603.12      2728503.94     10227193.07
      2728755.67     10226853.13
#Sta/Elev= 30
  4354.7 1213.63  4390.6 1212.96  4532.6 1206.91  4724.2 1202.13  4816.7 1198.34
  4823.2 1199.01  4859.7 1197.40  4880.6 1197.59  4901.4 1195.77  4944.4 1195.66
  4965.2 1193.24  5003.0 1192.07  5003.5 1189.07  5014.0 1189.07  5014.5 1192.07
  5044.2 1194.37  5129.8 1198.42  5144.4 1200.07  5179.9 1201.30  5200.7 1202.89
  5209.1 1204.48  5215.3 1204.13  5223.7 1205.35  5230.0 1204.59  5236.4 1206.69
  5244.6 1207.63  5285.2 1209.11  5394.9 1214.91  5406.7 1214.74  5423.0 1214.68
#Mann=5,-1,0
  4354.7    0.05       0  5003.0    0.03       0  5014.5    0.05       0
  5285.2    0.12       0  5406.7    0.05       0
Bank Sta=5003,5014.5
Exp/Cntr=0.3,0.1

Type RM Length L Ch R = 1,5500,500,500,500
BEGIN DESCRIPTION:
SAND CREEK 11.0
END DESCRIPTION:
XS GIS Cut Line= 3
      2728405.72     10227903.08      2728892.41     10227498.97
      2728995.25     10226966.41
#Sta/Elev= 30
  4367.4 1211.77  4374.5 1210.72  4403.2 1209.88  4424.0 1208.19  4431.8 1208.96
  4445.3 1208.09  4467.0 1208.49  4495.6 1207.09  4666.2 1205.53  4793.8 1201.91
  4829.0 1201.74  4935.7 1195.81  4950.1 1194.57  4964.4 1191.10  4970.9 1190.30
  5010.4 1190.01  5010.9 1187.01  5021.5 1187.01  5022.0 1190.01  5026.3 1191.19
  5047.7 1193.48  5094.4 1194.22  5099.5 1195.33  5151.4 1198.75  5189.3 1200.35
  5219.8 1202.94  5306.9 1207.63  5410.5 1211.94  5488.4 1212.61  5542.4 1212.54
#Mann=4,-1,0
  4367.4    0.05       0  5010.4    0.03       0  5022.0    0.05       0
  5488.4    0.12       0
Bank Sta=5010.4,5022
Exp/Cntr=0.3,0.1

Type RM Length L Ch R = 1,5000,500,500,500
BEGIN DESCRIPTION:
SAND CREEK 10.0
END DESCRIPTION:
XS GIS Cut Line= 3
      2729755.68     10228003.10      2729355.84     10227615.03
      2729082.38     10227008.09
#Sta/Elev= 30
  4442.8 1211.77  4471.0 1209.62  4478.2 1210.73  4492.3 1210.64  4513.4 1209.70
  4520.6 1207.98  4577.2 1207.94  4619.6 1205.33  4747.7 1200.59  4817.7 1198.40
  4871.9 1195.45  4930.6 1193.60  4966.1 1191.34  4980.3 1189.74  4981.4 1188.18
  4981.9 1185.18  4992.5 1185.18  4993.0 1188.18  5046.0 1191.29  5061.8 1191.62
  5078.9 1190.38  5108.1 1193.12  5113.6 1192.32  5122.7 1193.19  5136.7 1193.00
  5243.4 1198.42  5379.1 1203.66  5454.0 1206.08  5640.2 1209.66  5665.7 1209.79
#Mann=6,-1,0
  4442.8    0.05       0  4747.7    0.12       0  4871.9    0.05       0
  4981.4    0.03       0  4993.0    0.05       0  5640.2    0.12       0
Bank Sta=4981.4,4993
Exp/Cntr=0.3,0.1

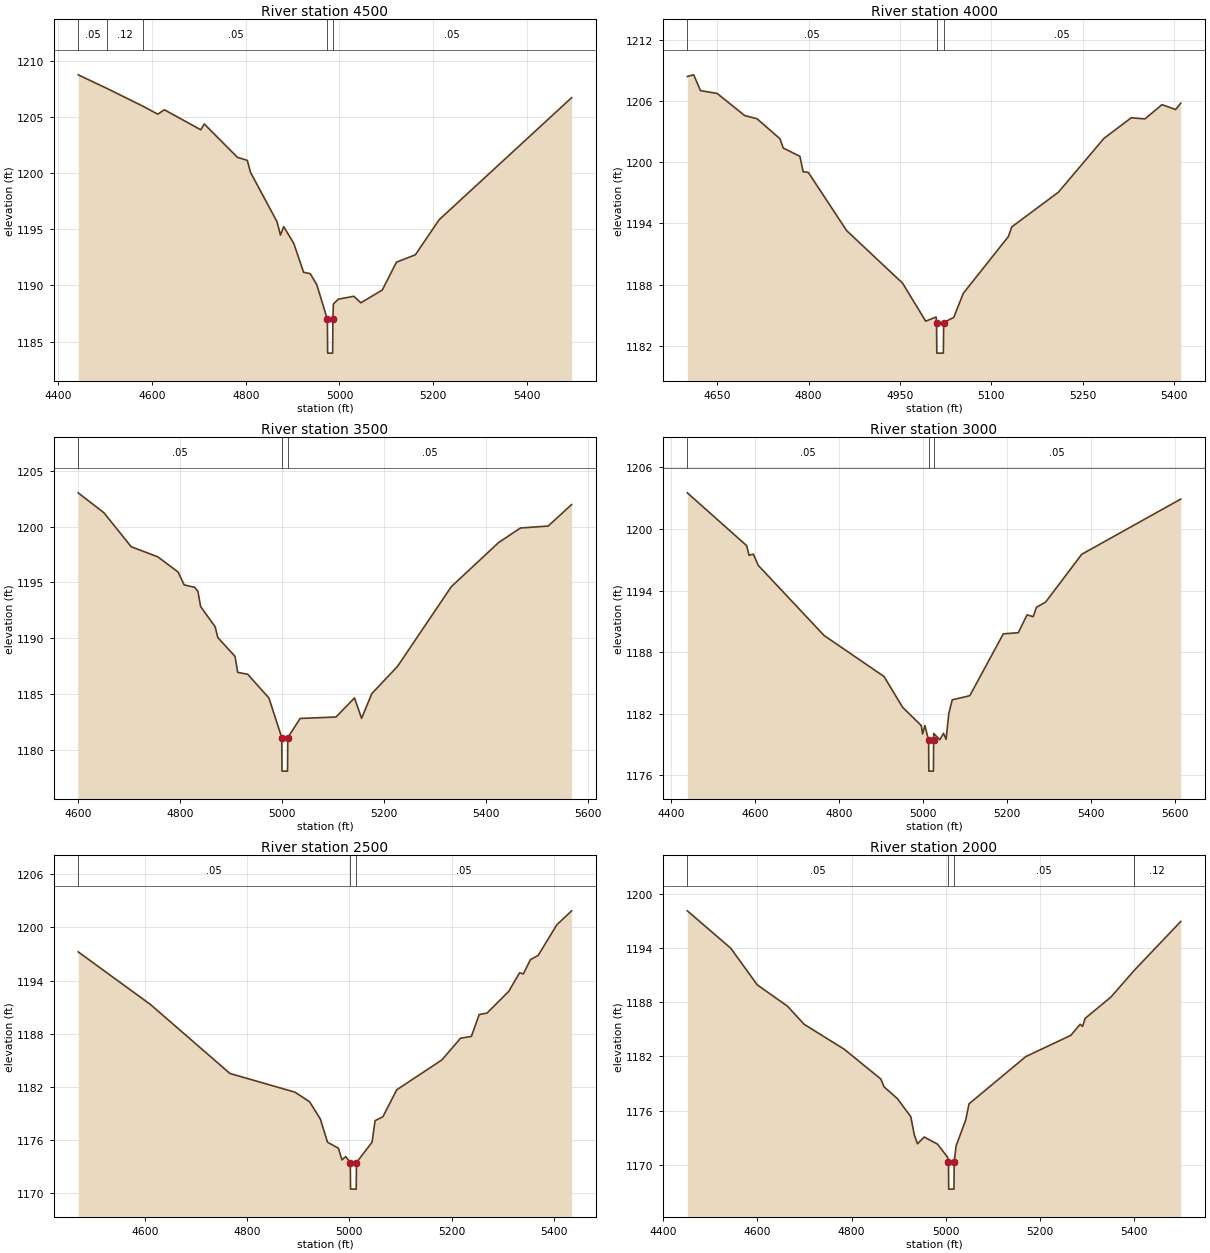
Type RM Length L Ch R = 1,4500,500,500,500
BEGIN DESCRIPTION:
SAND CREEK 9.0
END DESCRIPTION:
XS GIS Cut Line= 3
      2730105.66     10227703.08      2729727.23     10227293.42
      2729655.68     10226803.11
#Sta/Elev= 30
  4442.3 1208.73  4503.7 1207.52  4581.3 1205.92  4612.1 1205.23  4626.3 1205.62
  4703.9 1203.84  4711.3 1204.36  4782.2 1201.39  4803.2 1201.12  4810.0 1200.06
  4866.7 1195.66  4874.0 1194.47  4880.9 1195.22  4902.4 1193.74  4923.4 1191.16
  4937.6 1191.04  4951.7 1190.04  4974.2 1186.97  4974.7 1183.97  4985.4 1183.97
  4985.9 1186.97  4986.9 1188.34  4997.5 1188.77  5030.6 1189.03  5045.6 1188.45
  5091.3 1189.58  5121.6 1192.06  5162.0 1192.72  5212.5 1195.83  5495.5 1206.70
#Mann=5,-1,0
  4442.3    0.05       0  4503.7    0.12       0  4581.3    0.05       0
  4974.2    0.05       0  4985.9    0.05       0
Bank Sta=4974.2,4985.9
Exp/Cntr=0.3,0.1

Type RM Length L Ch R = 1,4000,500,500,500
BEGIN DESCRIPTION:
SAND CREEK 8.0
END DESCRIPTION:
XS GIS Cut Line= 3
      2730455.68     10227053.11      2730074.08     10226935.57
      2729705.69     10226753.11
#Sta/Elev= 30
  4600.7 1208.44  4611.2 1208.60  4622.3 1207.05  4649.7 1206.77  4694.9 1204.60
  4715.1 1204.29  4753.0 1202.31  4758.2 1201.41  4785.7 1200.59  4790.9 1199.08
  4799.5 1199.01  4862.3 1193.30  4954.3 1188.13  4992.2 1184.40  5009.4 1184.81
  5010.0 1184.26  5010.5 1181.26  5021.2 1181.26  5021.7 1184.26  5038.3 1184.77
  5054.0 1187.14  5128.0 1192.71  5133.6 1193.66  5210.2 1197.07  5285.0 1202.36
  5329.8 1204.38  5352.3 1204.27  5380.3 1205.67  5402.7 1205.19  5411.1 1205.81
#Mann=3,-1,0
  4600.7    0.05       0  5010.0    0.03       0  5021.7    0.05       0
Bank Sta=5010,5021.7
Exp/Cntr=0.3,0.1

Type RM Length L Ch R = 1,3500,500,500,500
BEGIN DESCRIPTION:
SAND CREEK 7.0
END DESCRIPTION:
XS GIS Cut Line= 3
      2730455.68     10226903.09      2730345.54     10226518.14
      2730405.68     10225953.13
#Sta/Elev= 30
  4599.6 1203.02  4650.2 1201.23  4703.6 1198.19  4755.6 1197.29  4795.8 1195.92
  4807.6 1194.77  4828.4 1194.55  4834.7 1194.17  4839.9 1192.83  4868.5 1191.01
  4873.7 1190.05  4907.5 1188.36  4912.7 1186.93  4932.4 1186.76  4974.0 1184.63
  4999.2 1181.08  4999.7 1178.08  5010.5 1178.08  5011.0 1181.08  5035.2 1182.80
  5105.6 1182.93  5142.0 1184.64  5155.9 1182.81  5176.0 1185.03  5226.3 1187.46
  5332.0 1194.61  5424.5 1198.55  5467.7 1199.87  5522.0 1200.04  5568.2 1201.97
#Mann=3,-1,0
  4599.6    0.05       0  4999.2    0.03       0  5011.0    0.05       0
Bank Sta=4999.2,5011
Exp/Cntr=0.3,0.1

Type RM Length L Ch R = 1,3000,500,500,500
BEGIN DESCRIPTION:
SAND CREEK 6.0
END DESCRIPTION:
XS GIS Cut Line= 3
      2730505.67     10226903.14      2730762.09     10226402.82
      2730405.67     10225903.10
#Sta/Elev= 30
  4437.8 1203.52  4579.3 1198.37  4584.9 1197.43  4595.1 1197.55  4607.1 1196.44
  4763.7 1189.62  4906.7 1185.62  4951.1 1182.61  4995.5 1180.84  4998.5 1180.02
  5004.1 1180.84  5012.9 1179.40  5013.4 1176.40  5024.3 1176.40  5024.8 1179.40
  5025.0 1180.07  5039.7 1179.46  5048.4 1180.09  5054.5 1179.50  5061.1 1182.02
  5069.2 1183.35  5111.0 1183.75  5190.9 1189.78  5226.6 1189.89  5247.5 1191.63
  5262.2 1191.45  5269.9 1192.37  5291.7 1192.87  5377.8 1197.53  5613.8 1202.91
#Mann=3,-1,0
  4437.8    0.05       0  5012.9    0.03       0  5024.8    0.05       0
Bank Sta=5012.9,5024.8
Exp/Cntr=0.3,0.1

Type RM Length L Ch R = 1,2500,500,500,500
BEGIN DESCRIPTION:
SAND CREEK 5.0
END DESCRIPTION:
XS GIS Cut Line= 3
      2730855.65     10226903.14      2731224.51     10226521.59
      2731455.69     10226153.10
#Sta/Elev= 30
  4469.3 1197.24  4610.7 1191.31  4766.3 1183.53  4893.7 1181.42  4922.0 1180.35
  4943.1 1178.41  4957.2 1175.78  4978.6 1175.10  4985.5 1173.78  4992.7 1174.16
  5001.8 1173.49  5002.3 1170.49  5013.4 1170.49  5013.9 1173.49  5044.4 1175.78
  5050.3 1178.21  5065.6 1178.65  5092.7 1181.69  5181.1 1185.06  5217.6 1187.51
  5238.8 1187.71  5254.1 1190.18  5269.4 1190.34  5311.9 1192.79  5333.1 1194.88
  5340.5 1194.76  5354.3 1196.36  5369.6 1196.85  5406.1 1200.30  5435.0 1201.87
#Mann=3,-1,0
  4469.3    0.05       0  5001.8    0.03       0  5013.9    0.05       0
Bank Sta=5001.8,5013.9
Exp/Cntr=0.3,0.1

Type RM Length L Ch R = 1,2000,500,500,500
BEGIN DESCRIPTION:
SAND CREEK 4.0
END DESCRIPTION:
XS GIS Cut Line= 3
      2731205.70     10227253.10      2731572.11     10226844.54
      2731655.69     10226353.09
#Sta/Elev= 30
  4451.2 1198.15  4543.5 1194.00  4599.6 1189.94  4663.9 1187.57  4699.0 1185.57
  4784.2 1182.80  4862.0 1179.49  4868.7 1178.63  4897.1 1177.32  4925.5 1175.32
  4933.0 1173.30  4939.7 1172.31  4953.9 1173.06  4982.3 1172.27  5003.3 1170.84
  5005.5 1170.28  5006.0 1167.28  5017.1 1167.28  5017.6 1170.28  5021.7 1172.08
  5042.0 1174.93  5049.1 1176.74  5169.6 1181.98  5265.2 1184.34  5285.1 1185.57
  5290.1 1185.33  5295.6 1186.22  5350.4 1188.59  5399.0 1191.50  5498.5 1196.97
#Mann=4,-1,0
  4451.2    0.05       0  5005.5    0.03       0  5017.6    0.05       0
  5399.0    0.12       0
Bank Sta=5005.5,5017.6
Exp/Cntr=0.3,0.1

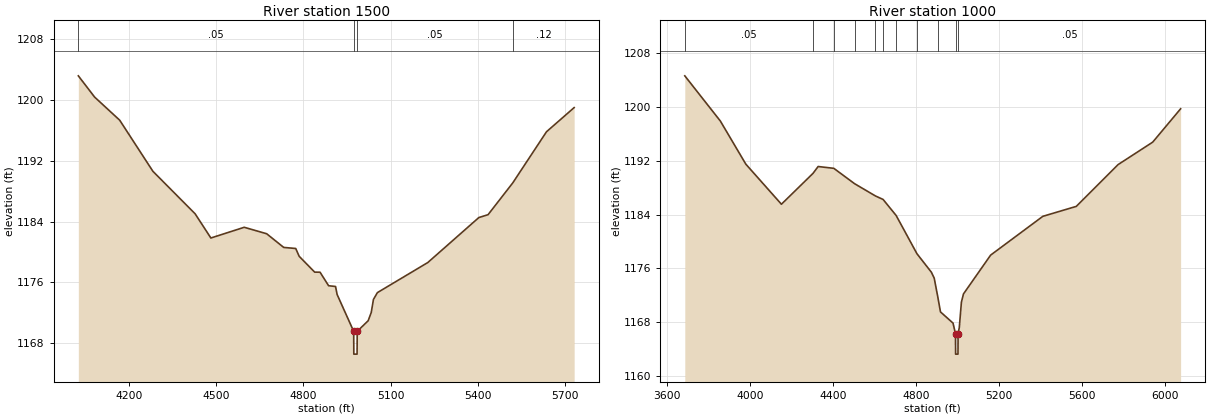
Type RM Length L Ch R = 1,1500,500,500,500
BEGIN DESCRIPTION:
SAND CREEK 3.0
END DESCRIPTION:
XS GIS Cut Line= 3
      2731144.04     10227366.18      2732044.87     10226994.75
      2731805.69     10226303.14
#Sta/Elev= 30
  4025.6 1203.18  4081.5 1200.39  4168.0 1197.34  4282.2 1190.62  4427.6 1185.02
  4481.7 1181.84  4596.5 1183.25  4673.7 1182.40  4732.4 1180.60  4773.7 1180.46
  4785.6 1179.43  4838.9 1177.35  4857.4 1177.34  4886.8 1175.56  4910.7 1175.46
  4916.1 1174.41  4973.1 1169.56  4973.6 1166.56  4984.8 1166.56  4985.3 1169.56
  5022.9 1170.95  5033.5 1172.03  5041.1 1173.75  5054.6 1174.65  5228.1 1178.61
  5403.8 1184.53  5435.6 1184.91  5520.7 1189.10  5636.6 1195.82  5731.8 1199.00
#Mann=4,-1,0
  4025.6    0.05       0  4973.1    0.03       0  4985.3    0.05       0
  5520.7    0.12       0
Bank Sta=4973.1,4985.3
Exp/Cntr=0.3,0.1

Type RM Length L Ch R = 1,1000,0,0,0
BEGIN DESCRIPTION:
SAND CREEK 2.0
END DESCRIPTION:
XS GIS Cut Line= 3
      2731144.02     10227420.44      2732446.51     10227252.27
      2732565.46     10226183.47
#Sta/Elev= 30
  3686.7 1204.66  3857.9 1197.93  3980.8 1191.50  4152.2 1185.53  4304.4 1190.13
  4329.1 1191.15  4404.6 1190.88  4504.7 1188.59  4604.8 1186.77  4642.1 1186.24
  4705.0 1183.85  4805.1 1178.16  4874.7 1175.40  4888.3 1174.52  4905.3 1171.77
  4918.5 1169.49  4979.0 1167.82  4990.9 1166.20  4991.4 1163.20  5002.8 1163.20
  5003.3 1166.20  5009.2 1167.18  5019.3 1170.95  5029.3 1172.17  5160.1 1177.95
  5411.7 1183.73  5572.7 1185.21  5773.9 1191.43  5940.9 1194.78  6075.4 1199.75
#Mann=11,-1,0
  3686.7    0.05       0  4304.4    0.12       0  4404.6    0.05       0
  4504.7    0.12       0  4604.8    0.05       0  4642.1    0.12       0
  4705.0    0.05       0  4805.1    0.12       0  4905.3    0.05       0
  4990.9    0.03       0  5003.3    0.05       0
Bank Sta=4990.9,5003.3
Exp/Cntr=0.3,0.1

Chan Stop Cuts=-1