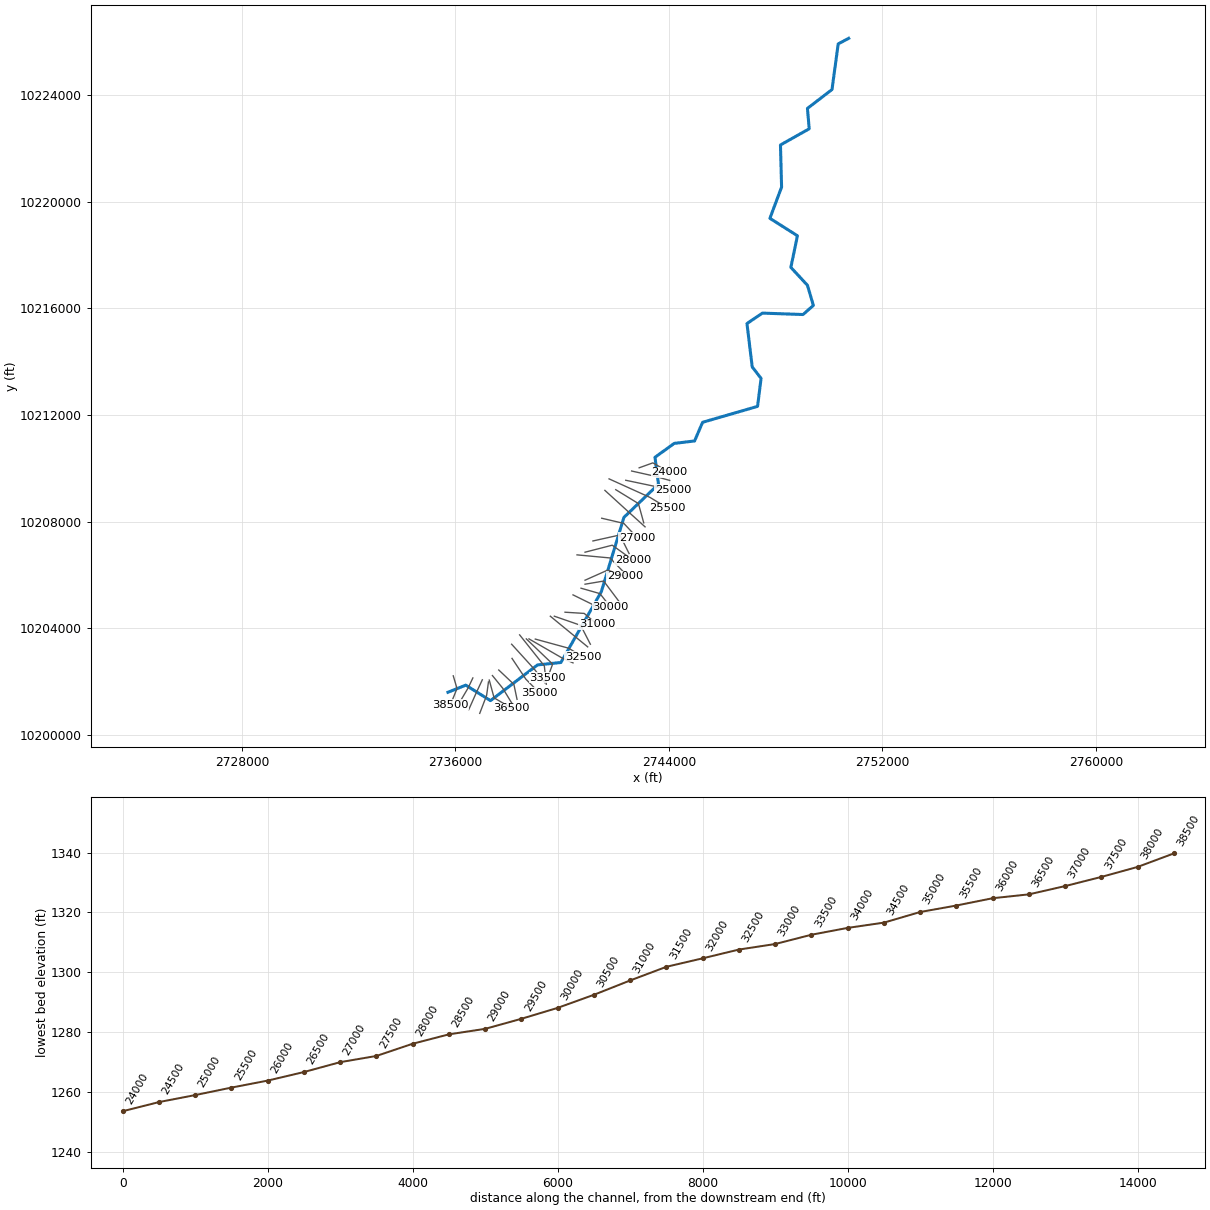
--- VASTERLING CREEK.prj (project) ---

Proj Title=VASTERLING CREEK Base Level Engineering
Current Plan=p01
Default Exp/Contr=0.3,0.1
English Units
Geom File=g01
Flow File=f01
Plan File=p01
BEGIN DESCRIPTION:
VASTERLING CREEK
END DESCRIPTION:

--- VASTERLING CREEK.p01 (plan) ---

Plan Title=Multiple Run
Short Identifier=Multiple
Geom File=g01
Flow File=f01
Subcritical Flow
K Sum by GR= 0
Std Step Tol= 0.01
Critical Tol= 0.01
Num of Std Step Trials= 20
Max Error Tol= 0.3
Flow Tol Ratio= 0.001
Split Flow NTrial= 30
Split Flow Tol= 0.02
Split Flow Ratio= 0.02
Log Output Level= 0
Friction Slope Method= 1
Unsteady Friction Slope Method= 2
Unsteady Bridges Friction Slope Method= 1
Parabolic Critical Depth
Global Vel Dist=  1 , 1 , 1
Global Log Level= 0
CheckData=True
Encroach Param= -1, 0, 0, 0
BEGIN DESCRIPTION:
Multiple Run
END DESCRIPTION:

--- VASTERLING CREEK.f01 (steady flow) ---

Flow Title=Multiple
Number of Profiles=7
Profile Names=10-year,25-year,50-year,1pct_min,100-year,1pct_plu,500-year
River Rch & RM= VASTERLING CREEK,Reach-1,38500
      66     127     199     103     312     942     821
River Rch & RM= VASTERLING CREEK,Reach-1,33000
     106     219     354     189     570    1720    1568
River Rch & RM= VASTERLING CREEK,Reach-1,23500
     122     257     419     224     677    2044    1884
River Rch & RM= VASTERLING CREEK,Reach-1,20000
     156     336     554     299     904    2730    2561
River Rch & RM= VASTERLING CREEK,Reach-1,19000
     188     412     683     372    1122    3389    3219
River Rch & RM= VASTERLING CREEK,Reach-1,14500
     218     483     806     440    1330    4017    3852
River Rch & RM= VASTERLING CREEK,Reach-1,11000
     242     539     903     495    1496    4518    4360
River Rch & RM= VASTERLING CREEK,Reach-1,5000
     266     597    1003     552    1667    5033    4884
Boundary for River Rch & Prof#=VASTERLING CREEK,Reach-1,1
Up Type=0
Dn Type=3
Dn Slope=0.005
Boundary for River Rch & Prof#=VASTERLING CREEK,Reach-1,2
Up Type=0
Dn Type=3
Dn Slope=0.005
Boundary for River Rch & Prof#=VASTERLING CREEK,Reach-1,3
Up Type=0
Dn Type=3
Dn Slope=0.005
Boundary for River Rch & Prof#=VASTERLING CREEK,Reach-1,4
Up Type=0
Dn Type=3
Dn Slope=0.005
Boundary for River Rch & Prof#=VASTERLING CREEK,Reach-1,5
Up Type=0
Dn Type=3
Dn Slope=0.005
Boundary for River Rch & Prof#=VASTERLING CREEK,Reach-1,6
Up Type=0
Dn Type=3
Dn Slope=0.005
Boundary for River Rch & Prof#=VASTERLING CREEK,Reach-1,7
Up Type=0
Dn Type=3
Dn Slope=0.005

--- VASTERLING CREEK.g01 (geometry) ---

Geom Title=Existing Conditions

River Reach=VASTERLING CREEK,Reach-1
Reach XY= 30
      2735718.50     10201601.00      2736386.00     10201868.00
      2737313.50     10201288.00      2739076.50     10202627.00
      2739951.50     10202718.00      2741467.00     10205374.00
      2742313.25     10208159.00      2743607.75     10209402.00
      2743476.50     10210412.00      2744198.25     10210933.00
      2744960.75     10211024.00      2745261.00     10211724.00
      2747320.25     10212321.00      2747451.50     10213371.00
      2747120.25     10213799.00      2746923.25     10215427.00
      2747501.50     10215818.00      2749023.50     10215765.00
      2749411.00     10216105.00      2749189.50     10216861.00
      2748568.00     10217533.00      2748814.00     10218718.00
      2747782.75     10219372.00      2748220.25     10220543.00
      2748178.25     10222122.00      2749255.00     10222730.00
      2749189.00     10223493.00      2750109.00     10224201.00
      2750341.50     10225913.00      2750733.50     10226121.00

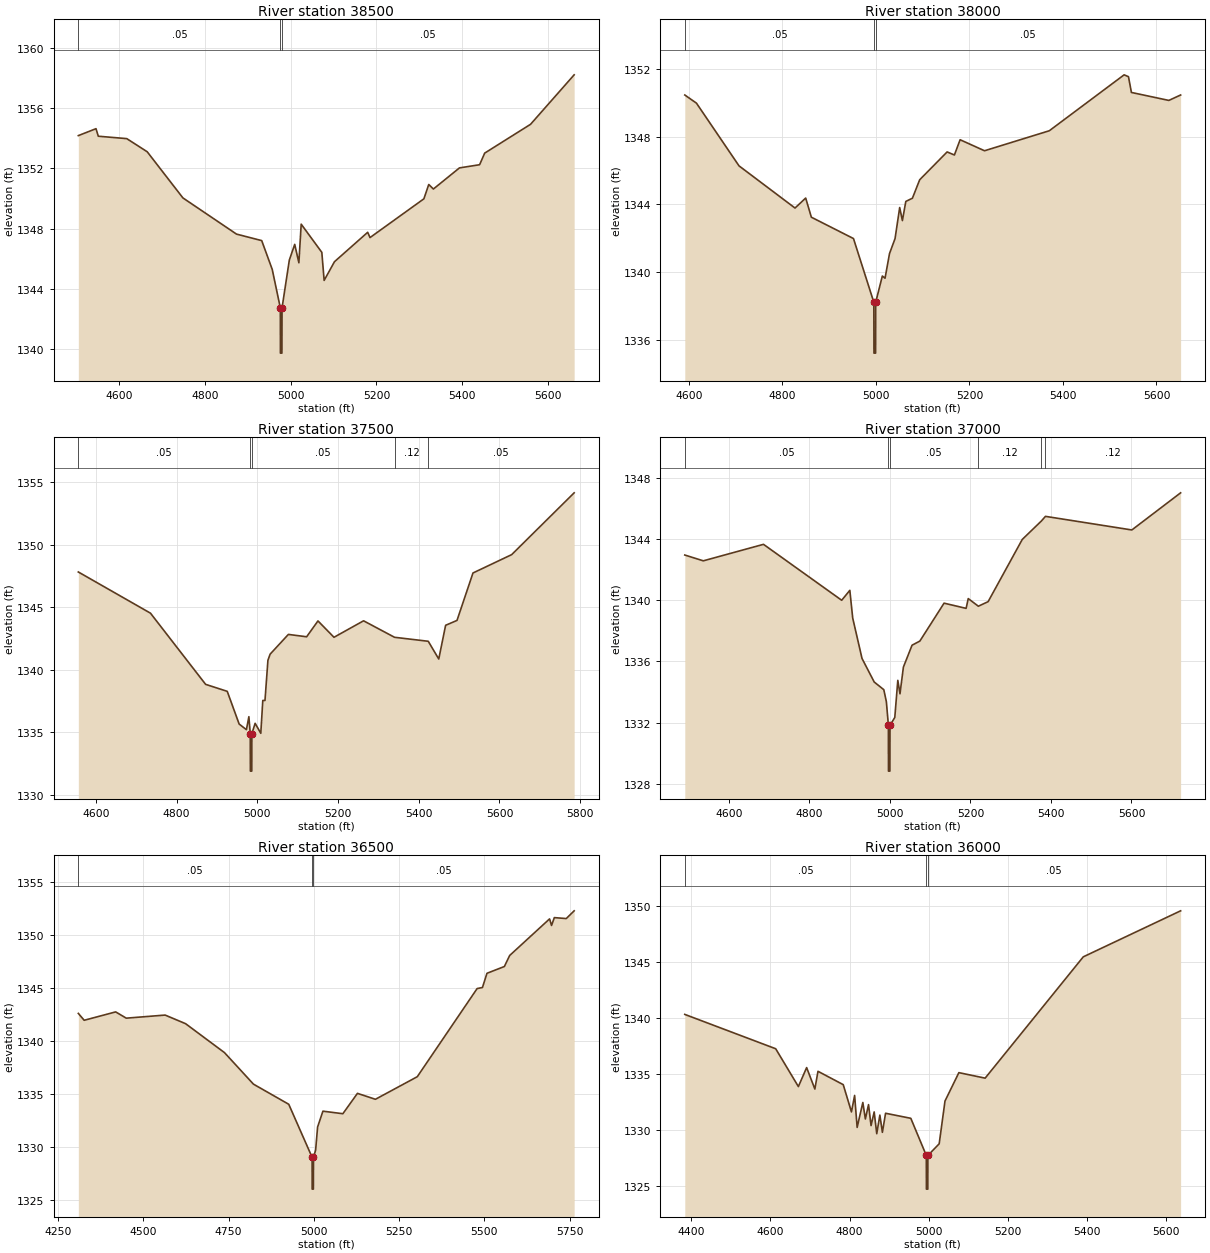
Type RM Length L Ch R = 1,38500,500,500,500
BEGIN DESCRIPTION:
VASTERLING CREEK 77.0
END DESCRIPTION:
XS GIS Cut Line= 3
      2735918.83     10202217.32      2736059.50     10201741.69
      2735810.49     10201128.52
#Sta/Elev= 30
  4504.0 1354.16  4545.3 1354.62  4550.6 1354.12  4617.1 1353.96  4664.8 1353.09
  4748.2 1350.03  4873.4 1347.63  4932.2 1347.20  4956.8 1345.29  4975.7 1342.74
  4975.9 1339.74  4979.4 1339.74  4979.7 1342.74  4996.7 1345.91  5009.3 1346.95
  5019.0 1345.73  5024.4 1348.29  5072.6 1346.42  5078.0 1344.56  5102.1 1345.80
  5179.7 1347.75  5185.1 1347.40  5310.9 1349.97  5322.3 1350.92  5333.1 1350.62
  5394.0 1352.02  5441.0 1352.23  5452.9 1353.00  5560.0 1354.91  5661.8 1358.19
#Mann=3,-1,0
  4504.0    0.05       0  4975.7    0.05       0  4979.7    0.05       0
Bank Sta=4975.7,4979.7
Exp/Cntr=0.3,0.1

Type RM Length L Ch R = 1,38000,500,500,500
BEGIN DESCRIPTION:
VASTERLING CREEK 76.0
END DESCRIPTION:
XS GIS Cut Line= 3
      2736652.52     10202138.00      2736478.76     10201768.30
      2736147.49     10201207.07
#Sta/Elev= 30
  4591.5 1350.45  4616.4 1349.97  4707.4 1346.27  4827.2 1343.78  4850.0 1344.37
  4862.1 1343.24  4952.2 1341.98  4995.7 1338.22  4996.0 1335.22  4999.5 1335.22
  4999.7 1338.22  5013.9 1339.77  5019.7 1339.64  5029.2 1341.09  5041.1 1341.98
  5051.0 1343.81  5056.8 1343.04  5064.1 1344.17  5078.2 1344.36  5093.8 1345.45
  5152.4 1347.09  5168.0 1346.91  5180.2 1347.81  5232.4 1347.16  5370.9 1348.34
  5530.9 1351.64  5540.2 1351.53  5546.5 1350.60  5626.5 1350.13  5651.7 1350.45
#Mann=3,-1,0
  4591.5    0.05       0  4995.7    0.05       0  4999.7    0.05       0
Bank Sta=4995.7,4999.7
Exp/Cntr=0.3,0.1

Type RM Length L Ch R = 1,37500,500,500,500
BEGIN DESCRIPTION:
VASTERLING CREEK 75.0
END DESCRIPTION:
XS GIS Cut Line= 3
      2737008.01     10202069.60      2736790.23     10201603.96
      2736499.26     10200951.34
#Sta/Elev= 30
  4556.4 1347.83  4735.2 1344.53  4871.8 1338.83  4925.4 1338.27  4954.9 1335.65
  4972.9 1335.20  4979.0 1336.24  4982.4 1334.88  4982.7 1331.88  4986.2 1331.88
  4986.4 1334.88  4994.5 1335.71  5008.5 1334.91  5013.5 1337.54  5018.9 1337.54
  5026.2 1340.76  5031.7 1341.25  5076.9 1342.83  5122.1 1342.64  5150.2 1343.91
  5189.9 1342.60  5263.2 1343.92  5339.9 1342.60  5423.5 1342.28  5449.5 1340.86
  5466.5 1343.56  5494.7 1343.95  5534.3 1347.75  5630.2 1349.22  5785.0 1354.17
#Mann=5,-1,0
  4556.4    0.05       0  4982.4    0.05       0  4986.4    0.05       0
  5339.9    0.12       0  5423.5    0.05       0
Bank Sta=4982.4,4986.4
Exp/Cntr=0.3,0.1

Type RM Length L Ch R = 1,37000,500,500,500
BEGIN DESCRIPTION:
VASTERLING CREEK 74.0
END DESCRIPTION:
XS GIS Cut Line= 3
      2737237.53     10201989.32      2737168.43     10201484.33
      2736910.50     10200809.86
#Sta/Elev= 30
  4490.3 1342.96  4536.3 1342.58  4685.8 1343.66  4880.1 1340.00  4900.3 1340.65
  4907.5 1338.83  4930.6 1336.19  4960.9 1334.65  4984.7 1334.15  4991.1 1333.36
  4996.1 1331.82  4996.3 1328.82  4999.8 1328.82  5000.1 1331.82  5012.0 1332.33
  5019.5 1334.76  5024.9 1333.88  5033.4 1335.63  5054.9 1337.06  5074.3 1337.33
  5134.4 1339.81  5189.2 1339.47  5194.5 1340.11  5219.6 1339.61  5243.9 1339.91
  5328.7 1343.98  5376.3 1345.19  5386.3 1345.49  5600.9 1344.60  5722.1 1347.03
#Mann=6,-1,0
  4490.3    0.05       0  4996.1    0.03       0  5000.1    0.05       0
  5219.6    0.12       0  5376.3    0.05       0  5386.3    0.12       0
Bank Sta=4996.1,5000.1
Exp/Cntr=0.3,0.1

Type RM Length L Ch R = 1,36500,500,500,500
BEGIN DESCRIPTION:
VASTERLING CREEK 73.0
END DESCRIPTION:
XS GIS Cut Line= 3
      2737267.27     10202058.73      2737448.67     10201392.27
      2738105.67     10201003.12
#Sta/Elev= 30
  4309.3 1342.62  4326.5 1341.97  4418.8 1342.76  4449.9 1342.17  4563.9 1342.46
  4623.9 1341.65  4738.0 1338.92  4822.9 1335.95  4926.5 1334.05  4995.0 1329.05
  4995.2 1326.05  4998.7 1326.05  4999.0 1329.05  5005.3 1329.73  5011.1 1331.91
  5026.7 1333.40  5085.2 1333.16  5128.0 1335.08  5180.7 1334.52  5303.5 1336.65
  5479.0 1344.96  5494.6 1345.06  5507.9 1346.40  5558.9 1347.04  5574.5 1348.08
  5691.5 1351.53  5697.3 1350.91  5705.5 1351.65  5740.4 1351.56  5763.6 1352.29
#Mann=3,-1,0
  4309.3    0.05       0  4995.0    0.05       0  4999.0    0.05       0
Bank Sta=4995,4999
Exp/Cntr=0.3,0.1

Type RM Length L Ch R = 1,36000,500,500,500
BEGIN DESCRIPTION:
VASTERLING CREEK 72.0
END DESCRIPTION:
XS GIS Cut Line= 3
      2737386.23     10202227.30      2737775.30     10201748.69
      2738105.68     10201203.13
#Sta/Elev= 30
  4383.2 1340.33  4613.2 1337.27  4670.6 1333.90  4691.5 1335.59  4712.3 1333.68
  4720.2 1335.26  4784.1 1334.07  4804.9 1331.64  4812.9 1333.11  4819.3 1330.26
  4833.7 1332.48  4840.1 1331.01  4848.1 1332.29  4854.5 1330.42  4862.4 1331.64
  4868.9 1329.70  4876.8 1331.36  4883.2 1329.82  4891.2 1331.52  4955.1 1331.07
  4994.3 1327.76  4994.6 1324.76  4998.1 1324.76  4998.3 1327.76  5026.9 1328.80
  5041.6 1332.61  5076.7 1335.14  5143.2 1334.65  5391.5 1345.46  5637.8 1349.56
#Mann=3,-1,0
  4383.2    0.05       0  4994.3    0.05       0  4998.3    0.05       0
Bank Sta=4994.3,4998.3
Exp/Cntr=0.3,0.1

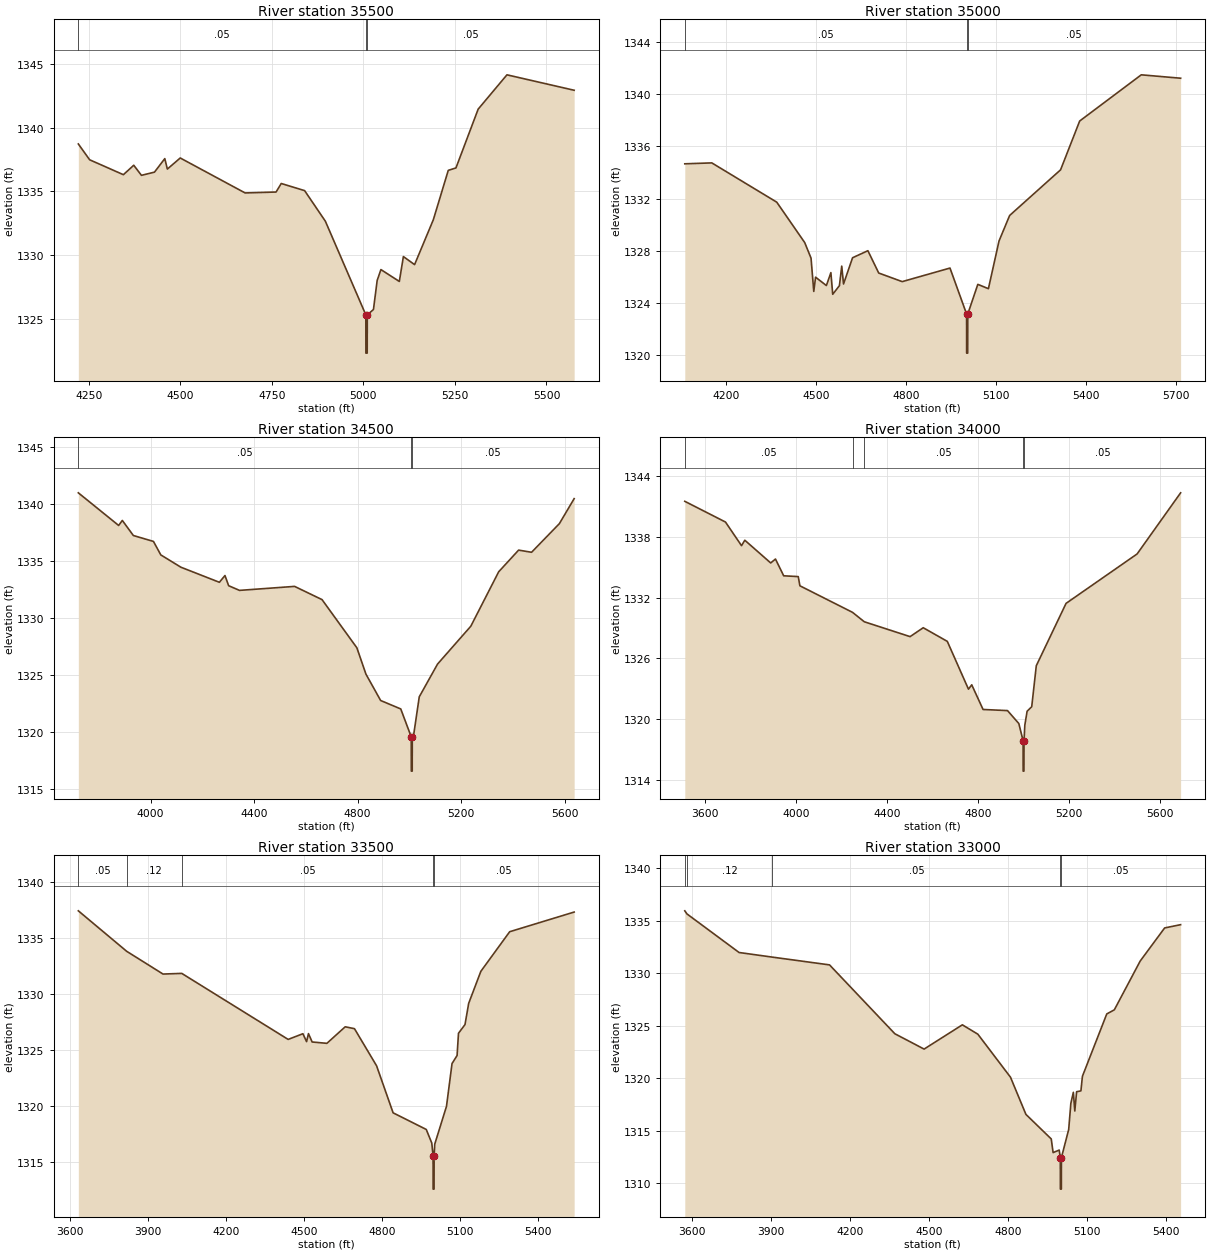
Type RM Length L Ch R = 1,35500,500,500,500
BEGIN DESCRIPTION:
VASTERLING CREEK 71.0
END DESCRIPTION:
XS GIS Cut Line= 3
      2737624.22     10202435.50      2738189.64     10201899.94
      2738308.02     10201336.54
#Sta/Elev= 30
  4221.2 1338.72  4252.1 1337.48  4344.3 1336.31  4372.6 1337.05  4393.6 1336.26
  4429.2 1336.51  4457.4 1337.57  4464.4 1336.75  4499.6 1337.62  4676.8 1334.88
  4761.4 1334.95  4775.5 1335.62  4839.4 1335.06  4896.1 1332.66  5006.6 1325.32
  5006.8 1322.32  5010.3 1322.32  5010.6 1325.32  5027.4 1325.74  5037.6 1328.02
  5047.8 1328.87  5098.1 1327.94  5109.2 1329.89  5139.8 1329.26  5190.9 1332.77
  5231.8 1336.65  5252.8 1336.84  5313.5 1341.45  5392.1 1344.14  5575.7 1342.93
#Mann=3,-1,0
  4221.2    0.05       0  5006.6    0.05       0  5010.6    0.05       0
Bank Sta=5006.6,5010.6
Exp/Cntr=0.3,0.1

Type RM Length L Ch R = 1,35000,500,500,500
BEGIN DESCRIPTION:
VASTERLING CREEK 70.0
END DESCRIPTION:
XS GIS Cut Line= 3
      2738119.99     10202871.75      2738639.07     10202092.39
      2739140.99     10201583.04
#Sta/Elev= 30
  4063.6 1334.66  4153.6 1334.73  4369.9 1331.72  4463.1 1328.62  4484.1 1327.43
  4493.2 1324.88  4499.2 1325.97  4535.2 1325.33  4550.2 1326.32  4556.3 1324.66
  4578.6 1325.32  4586.3 1326.82  4592.3 1325.45  4622.4 1327.46  4673.5 1328.00
  4709.5 1326.29  4787.7 1325.63  4946.9 1326.67  5002.2 1323.15  5002.4 1320.15
  5005.9 1320.15  5006.2 1323.15  5039.6 1325.42  5074.9 1325.09  5110.3 1328.75
  5145.6 1330.70  5315.3 1334.20  5378.9 1337.94  5584.0 1341.48  5715.1 1341.22
#Mann=3,-1,0
  4063.6    0.05       0  5002.2    0.05       0  5006.2    0.05       0
Bank Sta=5002.2,5006.2
Exp/Cntr=0.3,0.1

Type RM Length L Ch R = 1,34500,500,500,500
BEGIN DESCRIPTION:
VASTERLING CREEK 69.0
END DESCRIPTION:
XS GIS Cut Line= 3
      2738105.66     10203403.14      2738965.72     10202456.63
      2739355.70     10201953.09
#Sta/Elev= 30
  3721.1 1340.99  3876.9 1338.13  3891.1 1338.57  3933.7 1337.25  4011.4 1336.73
  4039.8 1335.55  4117.5 1334.47  4266.1 1333.15  4287.7 1333.74  4301.9 1332.85
  4343.8 1332.44  4556.7 1332.79  4662.8 1331.63  4797.3 1327.41  4832.4 1325.10
  4889.2 1322.79  4966.9 1322.05  5007.4 1319.60  5007.7 1316.60  5011.2 1316.60
  5011.4 1319.60  5017.1 1319.82  5038.4 1323.11  5109.0 1325.98  5237.6 1329.30
  5345.3 1334.07  5422.3 1335.97  5472.4 1335.78  5579.8 1338.29  5636.9 1340.48
#Mann=3,-1,0
  3721.1    0.05       0  5007.4    0.03       0  5011.4    0.05       0
Bank Sta=5007.4,5011.4
Exp/Cntr=0.3,0.1

Type RM Length L Ch R = 1,34000,500,500,500
BEGIN DESCRIPTION:
VASTERLING CREEK 68.0
END DESCRIPTION:
XS GIS Cut Line= 3
      2738405.70     10203753.09      2739331.33     10202588.16
      2739405.69     10201903.08
#Sta/Elev= 30
  3512.1 1341.54  3690.7 1339.49  3761.2 1337.15  3775.6 1337.69  3889.3 1335.44
  3910.2 1335.83  3946.3 1334.17  4010.2 1334.09  4017.5 1333.18  4248.7 1330.55
  4300.2 1329.62  4501.3 1328.15  4559.0 1329.03  4664.7 1327.68  4757.6 1322.95
  4772.0 1323.38  4821.7 1320.94  4929.0 1320.83  4978.7 1319.55  4997.5 1317.84
  4997.7 1314.84  5001.2 1314.84  5001.5 1317.84  5005.1 1319.40  5015.1 1320.77
  5035.3 1321.21  5055.4 1325.27  5186.1 1331.44  5498.0 1336.33  5689.1 1342.38
#Mann=5,-1,0
  3512.1    0.05       0  4248.7    0.12       0  4300.2    0.05       0
  4997.5    0.05       0  5001.5    0.05       0
Bank Sta=4997.5,5001.5
Exp/Cntr=0.3,0.1

Type RM Length L Ch R = 1,33500,500,500,500
BEGIN DESCRIPTION:
VASTERLING CREEK 67.0
END DESCRIPTION:
XS GIS Cut Line= 3
      2738655.68     10203603.12      2739642.71     10202658.23
      2739455.69     10202153.14
#Sta/Elev= 30
  3633.6 1337.46  3819.2 1333.84  3959.0 1331.80  4031.0 1331.86  4439.8 1325.95
  4496.4 1326.46  4510.6 1325.75  4517.8 1326.47  4532.0 1325.72  4588.6 1325.60
  4659.0 1327.08  4694.6 1326.91  4779.5 1323.59  4843.0 1319.38  4970.4 1317.89
  4991.5 1316.68  4996.6 1315.55  4996.8 1312.55  5000.3 1312.55  5000.6 1315.55
  5003.0 1316.58  5048.1 1319.96  5069.4 1323.79  5088.8 1324.51  5094.2 1326.50
  5119.2 1327.28  5133.4 1329.18  5180.0 1332.04  5290.9 1335.59  5538.6 1337.35
#Mann=5,-1,0
  3633.6    0.05       0  3819.2    0.12       0  4031.0    0.05       0
  4996.6    0.03       0  5000.6    0.05       0
Bank Sta=4996.6,5000.6
Exp/Cntr=0.3,0.1

Type RM Length L Ch R = 1,33000,500,500,500
BEGIN DESCRIPTION:
VASTERLING CREEK 66.0
END DESCRIPTION:
XS GIS Cut Line= 3
      2738755.66     10203603.13      2739991.46     10202889.00
      2740405.66     10202703.12
#Sta/Elev= 30
  3572.7 1335.96  3580.7 1335.67  3778.7 1331.99  3904.9 1331.55  4121.9 1330.81
  4369.7 1324.25  4480.7 1322.79  4625.8 1325.10  4684.6 1324.21  4808.5 1320.11
  4867.0 1316.57  4963.1 1314.23  4970.2 1312.93  4993.3 1313.17  4997.5 1312.45
  4997.8 1309.45  5001.4 1309.45  5001.7 1312.45  5029.3 1315.13  5037.5 1317.62
  5047.0 1318.67  5052.5 1316.89  5059.4 1318.73  5075.7 1318.81  5081.4 1320.20
  5173.8 1326.14  5202.5 1326.53  5300.7 1331.18  5393.4 1334.33  5454.0 1334.64
#Mann=5,-1,0
  3572.7    0.05       0  3580.7    0.12       0  3904.9    0.05       0
  4997.5    0.03       0  5001.7    0.05       0
Bank Sta=4997.5,5001.7
Exp/Cntr=0.3,0.1

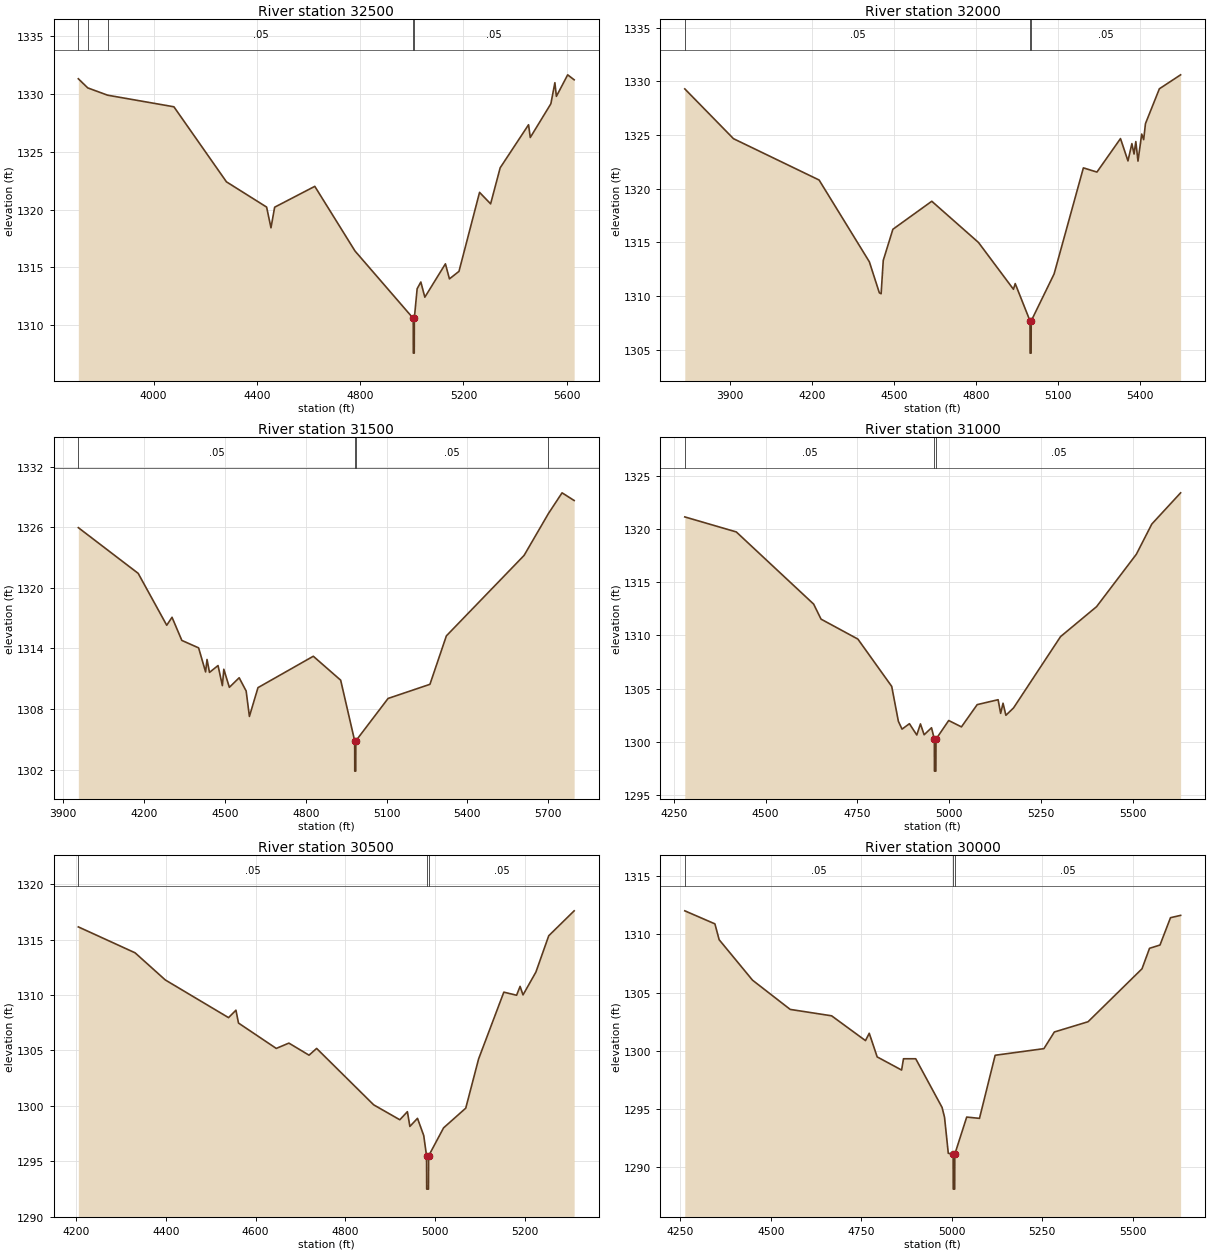
Type RM Length L Ch R = 1,32500,500,500,500
BEGIN DESCRIPTION:
VASTERLING CREEK 65.0
END DESCRIPTION:
XS GIS Cut Line= 3
      2738992.48     10203595.57      2740237.89     10203254.39
      2740777.20     10202931.27
#Sta/Elev= 30
  3708.7 1331.29  3745.3 1330.50  3822.4 1329.87  4078.8 1328.87  4282.3 1322.39
  4437.8 1320.21  4454.7 1318.42  4468.9 1320.20  4624.4 1322.00  4780.0 1316.42
  5005.6 1310.60  5005.9 1307.60  5009.5 1307.60  5009.8 1310.60  5020.7 1313.16
  5035.0 1313.74  5050.5 1312.43  5130.2 1315.31  5145.8 1314.01  5182.7 1314.66
  5262.4 1321.48  5305.2 1320.49  5342.2 1323.60  5452.1 1327.32  5458.8 1326.22
  5538.5 1329.13  5554.1 1330.95  5559.9 1329.77  5603.6 1331.63  5628.7 1331.20
#Mann=5,-1,0
  3708.7    0.05       0  3745.3    0.12       0  3822.4    0.05       0
  5005.6    0.03       0  5009.8    0.05       0
Bank Sta=5005.6,5009.8
Exp/Cntr=0.3,0.1

Type RM Length L Ch R = 1,32000,500,500,500
BEGIN DESCRIPTION:
VASTERLING CREEK 64.0
END DESCRIPTION:
XS GIS Cut Line= 3
      2739555.69     10204453.10      2740532.42     10203649.53
      2740955.72     10203303.08
#Sta/Elev= 30
  3735.2 1329.29  3913.1 1324.65  4225.9 1320.80  4409.6 1313.18  4446.1 1310.29
  4452.6 1310.20  4460.4 1313.31  4495.6 1316.21  4637.7 1318.82  4808.4 1314.98
  4936.1 1310.62  4942.6 1311.15  4996.7 1307.67  4997.0 1304.67  5000.7 1304.67
  5001.0 1307.67  5084.7 1312.05  5191.7 1321.93  5241.2 1321.54  5327.3 1324.66
  5354.6 1322.58  5368.9 1324.19  5376.8 1323.22  5383.3 1324.38  5391.2 1322.56
  5404.8 1325.08  5412.0 1324.56  5418.5 1326.05  5469.4 1329.30  5547.0 1330.60
#Mann=3,-1,0
  3735.2    0.05       0  4996.7    0.05       0  5001.0    0.05       0
Bank Sta=4996.7,5001
Exp/Cntr=0.3,0.1

Type RM Length L Ch R = 1,31500,500,500,500
BEGIN DESCRIPTION:
VASTERLING CREEK 63.0
END DESCRIPTION:
XS GIS Cut Line= 3
      2739705.70     10204453.11      2740692.12     10204111.51
      2741055.66     10203403.15
#Sta/Elev= 30
  3956.1 1325.96  4178.3 1321.43  4284.2 1316.29  4303.8 1317.08  4340.2 1314.79
  4402.5 1314.05  4428.4 1311.67  4433.7 1312.90  4442.9 1311.62  4474.6 1312.30
  4490.7 1310.31  4496.0 1311.93  4516.6 1310.14  4553.0 1311.09  4578.9 1309.78
  4591.0 1307.26  4622.8 1310.11  4828.1 1313.22  4929.7 1310.85  4981.7 1304.84
  4982.0 1301.84  4985.7 1301.84  4986.0 1304.84  5105.7 1309.04  5261.0 1310.44
  5322.0 1315.24  5610.4 1323.21  5700.3 1327.34  5751.3 1329.41  5796.2 1328.65
#Mann=4,-1,0
  3956.1    0.05       0  4981.7    0.05       0  4986.0    0.05       0
  5700.3    0.12       0
Bank Sta=4981.7,4986
Exp/Cntr=0.3,0.1

Type RM Length L Ch R = 1,31000,500,500,500
BEGIN DESCRIPTION:
VASTERLING CREEK 62.0
END DESCRIPTION:
XS GIS Cut Line= 3
      2740105.73     10204603.11      2740824.22     10204558.12
      2741305.72     10204153.08
#Sta/Elev= 30
  4280.1 1321.12  4420.3 1319.71  4630.7 1312.94  4650.8 1311.53  4751.0 1309.66
  4843.1 1305.22  4861.2 1301.95  4871.2 1301.21  4891.3 1301.72  4911.3 1300.66
  4921.3 1301.70  4931.3 1300.68  4951.4 1301.34  4959.1 1300.27  4959.4 1297.27
  4963.3 1297.27  4963.6 1300.27  4998.2 1302.02  5032.8 1301.42  5075.7 1303.51
  5132.6 1303.97  5139.5 1302.69  5146.0 1303.64  5153.8 1302.51  5174.6 1303.20
  5302.5 1309.89  5400.5 1312.70  5508.8 1317.62  5550.8 1320.45  5629.2 1323.38
#Mann=3,-1,0
  4280.1    0.05       0  4959.1    0.05       0  4963.6    0.05       0
Bank Sta=4959.1,4963.6
Exp/Cntr=0.3,0.1

Type RM Length L Ch R = 1,30500,500,500,500
BEGIN DESCRIPTION:
VASTERLING CREEK 61.0
END DESCRIPTION:
XS GIS Cut Line= 3
      2740405.66     10205253.13      2741118.64     10204901.90
      2741355.71     10204703.09
#Sta/Elev= 30
  4205.2 1316.15  4331.6 1313.81  4398.9 1311.36  4539.7 1307.96  4556.2 1308.63
  4561.9 1307.47  4646.0 1305.18  4674.1 1305.66  4719.0 1304.57  4735.9 1305.18
  4862.9 1300.09  4921.2 1298.74  4938.0 1299.47  4943.6 1298.14  4960.5 1298.87
  4974.4 1297.32  4980.7 1295.48  4981.0 1292.48  4984.9 1292.48  4985.3 1295.48
  5018.6 1298.01  5068.0 1299.79  5096.6 1304.23  5152.8 1310.26  5181.2 1309.98
  5189.0 1310.78  5195.5 1310.01  5224.2 1312.07  5252.8 1315.35  5309.4 1317.60
#Mann=3,-1,0
  4205.2    0.05       0  4980.7    0.03       0  4985.3    0.05       0
Bank Sta=4980.7,4985.3
Exp/Cntr=0.3,0.1

Type RM Length L Ch R = 1,30000,500,500,500
BEGIN DESCRIPTION:
VASTERLING CREEK 60.0
END DESCRIPTION:
XS GIS Cut Line= 3
      2740705.66     10205503.12      2741415.02     10205300.27
      2741805.69     10204803.10
#Sta/Elev= 30
  4262.2 1312.02  4345.4 1310.90  4357.1 1309.54  4449.4 1306.06  4553.5 1303.55
  4667.9 1303.00  4761.5 1300.87  4771.9 1301.50  4793.8 1299.47  4861.3 1298.34
  4866.5 1299.31  4900.3 1299.31  4973.1 1295.13  4979.9 1294.29  4990.3 1291.19
  5003.7 1291.11  5004.0 1288.11  5008.0 1288.11  5008.3 1291.11  5041.2 1294.30
  5076.5 1294.19  5119.8 1299.61  5254.5 1300.18  5283.4 1301.61  5376.5 1302.49
  5525.6 1307.04  5546.4 1308.80  5575.3 1309.08  5604.3 1311.43  5632.3 1311.63
#Mann=3,-1,0
  4262.2    0.05       0  5003.7    0.05       0  5008.3    0.05       0
Bank Sta=5003.7,5008.3
Exp/Cntr=0.3,0.1

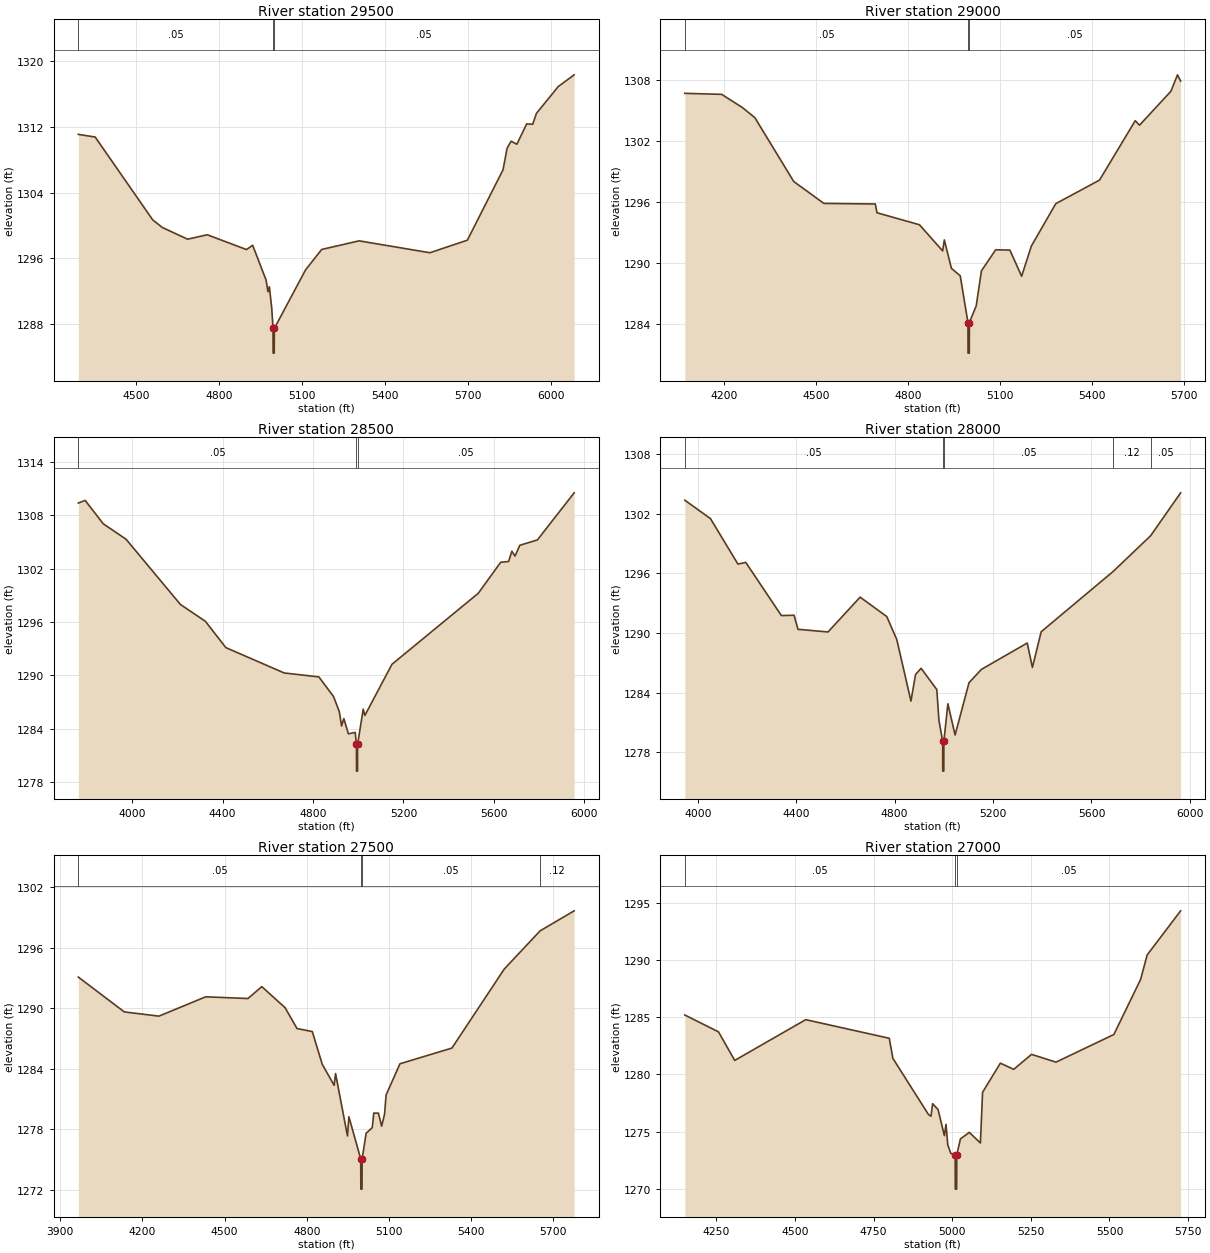
Type RM Length L Ch R = 1,29500,500,500,500
BEGIN DESCRIPTION:
VASTERLING CREEK 59.0
END DESCRIPTION:
XS GIS Cut Line= 3
      2740855.67     10205653.11      2741554.79     10205771.65
      2742205.70     10204903.09
#Sta/Elev= 30
  4290.9 1311.09  4351.8 1310.77  4559.9 1300.69  4595.2 1299.75  4686.5 1298.33
  4757.5 1298.87  4899.5 1297.07  4921.9 1297.59  4970.5 1293.35  4977.2 1291.94
  4982.3 1292.54  4990.8 1289.97  4995.6 1287.46  4995.9 1284.46  4999.9 1284.46
  5000.2 1287.46  5113.4 1294.60  5171.7 1297.08  5307.2 1298.13  5563.4 1296.68
  5698.9 1298.21  5828.0 1306.78  5842.6 1309.39  5857.2 1310.26  5878.1 1309.89
  5913.5 1312.37  5935.4 1312.32  5948.9 1313.65  6028.1 1316.92  6085.4 1318.34
#Mann=3,-1,0
  4290.9    0.05       0  4995.6    0.05       0  5000.2    0.05       0
Bank Sta=4995.6,5000.2
Exp/Cntr=0.3,0.1

Type RM Length L Ch R = 1,29000,500,500,500
BEGIN DESCRIPTION:
VASTERLING CREEK 58.0
END DESCRIPTION:
XS GIS Cut Line= 3
      2740855.69     10205803.11      2741704.18     10206181.65
      2742355.66     10205953.12
#Sta/Elev= 30
  4070.9 1306.64  4191.3 1306.54  4258.7 1305.25  4299.7 1304.25  4426.8 1297.97
  4525.1 1295.82  4693.2 1295.76  4698.7 1294.90  4837.4 1293.72  4913.1 1291.15
  4918.6 1292.23  4941.8 1289.43  4970.5 1288.71  4995.8 1284.10  4996.1 1281.10
  5000.1 1281.10  5000.4 1284.10  5022.8 1285.75  5039.8 1289.19  5086.4 1291.26
  5132.8 1291.23  5171.1 1288.66  5202.9 1291.63  5282.5 1295.79  5425.5 1298.11
  5542.1 1303.95  5556.2 1303.51  5658.6 1306.84  5680.2 1308.46  5690.4 1307.84
#Mann=3,-1,0
  4070.9    0.05       0  4995.8    0.05       0  5000.4    0.05       0
Bank Sta=4995.8,5000.4
Exp/Cntr=0.3,0.1

Type RM Length L Ch R = 1,28500,500,500,500
BEGIN DESCRIPTION:
VASTERLING CREEK 57.0
END DESCRIPTION:
XS GIS Cut Line= 3
      2740555.67     10206753.11      2741789.00     10206637.90
      2742455.67     10205953.13
#Sta/Elev= 30
  3761.3 1309.36  3791.4 1309.66  3871.8 1307.03  3972.2 1305.31  4213.3 1297.97
  4323.8 1296.08  4414.1 1293.13  4672.7 1290.28  4825.9 1289.84  4890.7 1287.64
  4916.3 1285.94  4926.4 1284.33  4936.4 1285.16  4956.5 1283.45  4986.6 1283.61
  4992.2 1282.26  4992.6 1279.26  4996.8 1279.26  4997.2 1282.26  5022.2 1286.22
  5029.4 1285.51  5149.5 1291.26  5531.4 1299.23  5630.5 1302.71  5665.7 1302.80
  5679.9 1303.95  5694.0 1303.41  5715.3 1304.62  5793.0 1305.22  5955.7 1310.51
#Mann=3,-1,0
  3761.3    0.05       0  4992.2    0.03       0  4997.2    0.05       0
Bank Sta=4992.2,4997.2
Exp/Cntr=0.3,0.1

Type RM Length L Ch R = 1,28000,500,500,500
BEGIN DESCRIPTION:
VASTERLING CREEK 56.0
END DESCRIPTION:
XS GIS Cut Line= 3
      2740855.66     10206853.11      2741875.09     10207116.05
      2742655.68     10206553.11
#Sta/Elev= 30
  3947.2 1303.34  4051.5 1301.49  4163.2 1296.92  4195.1 1297.09  4339.7 1291.75
  4391.3 1291.78  4407.2 1290.37  4529.3 1290.10  4659.8 1293.60  4768.1 1291.65
  4808.8 1289.34  4866.4 1283.16  4885.0 1285.83  4907.7 1286.45  4971.5 1284.31
  4980.0 1281.25  4995.2 1279.12  4995.6 1276.12  4999.9 1276.12  5000.2 1279.12
  5016.4 1282.89  5045.8 1279.75  5102.3 1285.00  5152.6 1286.34  5339.1 1288.99
  5360.0 1286.53  5395.6 1290.12  5687.7 1296.17  5840.6 1299.77  5962.4 1304.08
#Mann=5,-1,0
  3947.2    0.05       0  4995.2    0.03       0  5000.2    0.05       0
  5687.7    0.12       0  5840.6    0.05       0
Bank Sta=4995.2,5000.2
Exp/Cntr=0.3,0.1

Type RM Length L Ch R = 1,27500,500,500,500
BEGIN DESCRIPTION:
VASTERLING CREEK 55.0
END DESCRIPTION:
XS GIS Cut Line= 3
      2741151.71     10207274.58      2742161.04     10207499.11
      2742505.70     10206803.07
#Sta/Elev= 30
  3966.0 1293.10  4134.0 1289.64  4260.3 1289.22  4431.1 1291.14  4585.4 1290.97
  4636.0 1292.15  4721.1 1290.06  4764.6 1287.99  4820.4 1287.69  4856.7 1284.44
  4900.2 1282.35  4905.4 1283.52  4948.9 1277.32  4954.0 1279.23  4997.3 1275.04
  4997.7 1272.04  5002.0 1272.04  5002.4 1275.04  5017.0 1277.59  5039.4 1278.15
  5045.0 1279.59  5061.9 1279.59  5073.6 1278.29  5084.3 1279.48  5089.9 1281.39
  5140.6 1284.49  5330.3 1286.05  5521.5 1293.90  5652.3 1297.69  5776.7 1299.68
#Mann=4,-1,0
  3966.0    0.05       0  4997.3    0.03       0  5002.4    0.05       0
  5652.3    0.12       0
Bank Sta=4997.3,5002.4
Exp/Cntr=0.3,0.1

Type RM Length L Ch R = 1,27000,500,500,500
BEGIN DESCRIPTION:
VASTERLING CREEK 54.0
END DESCRIPTION:
XS GIS Cut Line= 3
      2741481.18     10208126.78      2742309.52     10207933.46
      2742805.72     10207403.08
#Sta/Elev= 30
  4149.4 1285.21  4256.7 1283.73  4308.1 1281.23  4534.0 1284.80  4799.7 1283.17
  4811.2 1281.41  4924.2 1276.50  4932.4 1276.35  4937.6 1277.44  4955.0 1276.92
  4975.0 1274.64  4980.1 1275.63  4985.8 1273.83  4995.5 1273.09  5009.3 1272.96
  5009.7 1269.96  5014.0 1269.96  5014.4 1272.96  5026.0 1274.36  5054.3 1274.93
  5089.5 1274.00  5096.4 1278.44  5153.0 1280.99  5195.5 1280.45  5252.2 1281.76
  5329.9 1281.08  5514.0 1283.50  5599.0 1288.32  5620.0 1290.47  5726.3 1294.33
#Mann=3,-1,0
  4149.4    0.05       0  5009.3    0.03       0  5014.4    0.05       0
Bank Sta=5009.3,5014.4
Exp/Cntr=0.3,0.1

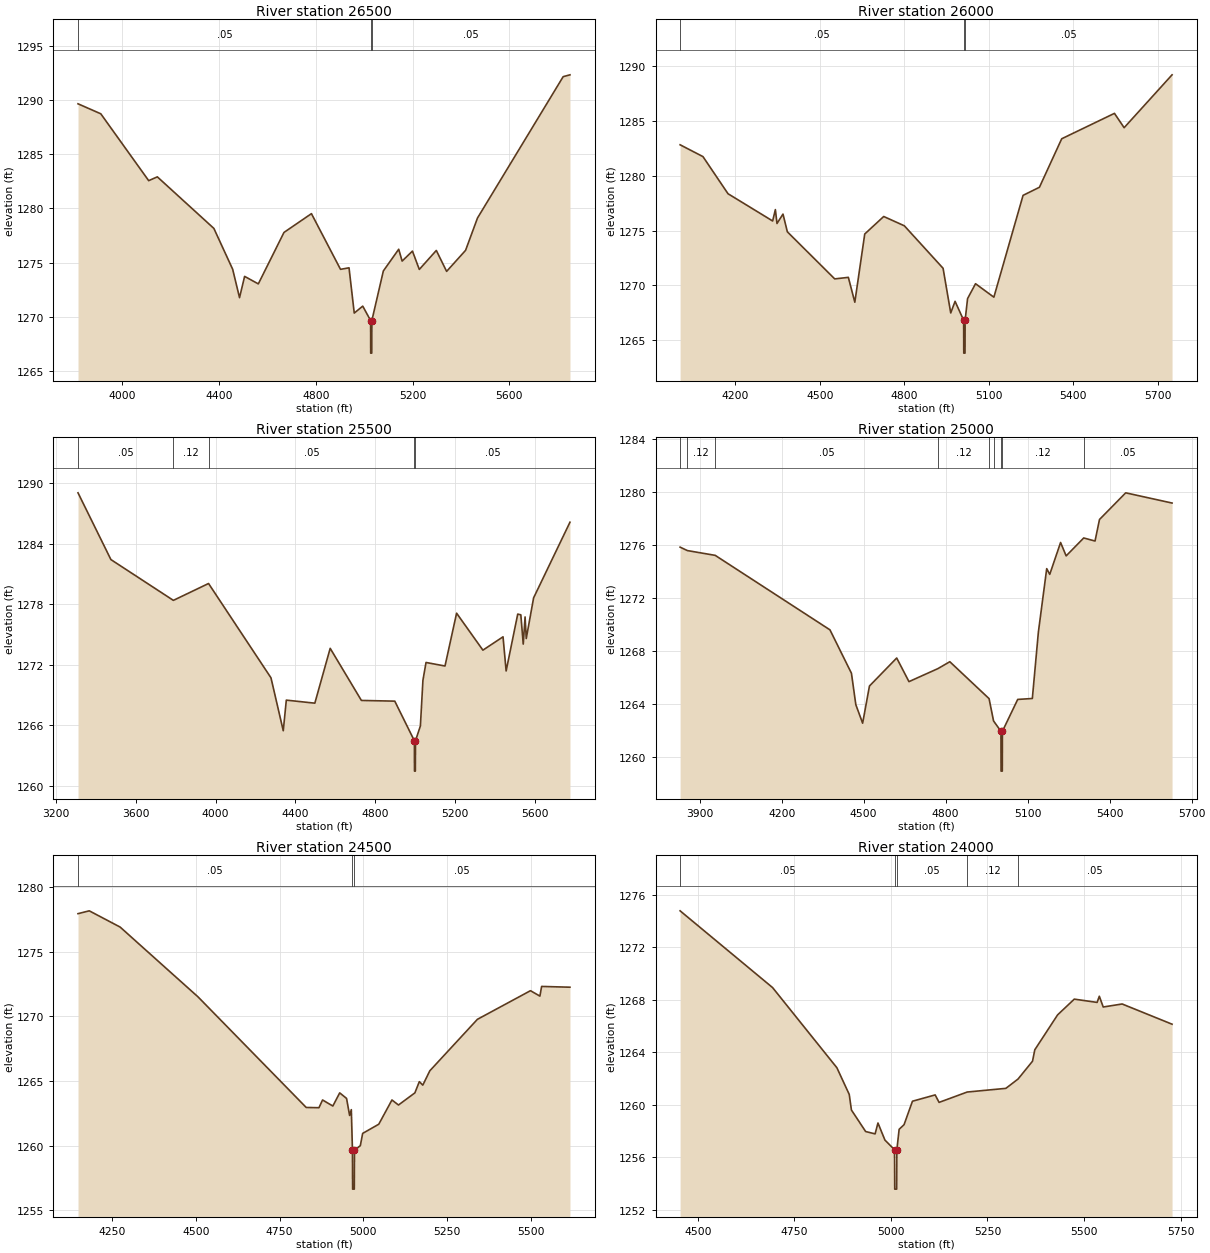
Type RM Length L Ch R = 1,26500,500,500,500
BEGIN DESCRIPTION:
VASTERLING CREEK 53.0
END DESCRIPTION:
XS GIS Cut Line= 3
      2741600.44     10209171.03      2742474.76     10208373.23
      2743105.72     10207803.08
#Sta/Elev= 30
  3816.4 1289.63  3910.6 1288.71  4108.6 1282.55  4144.4 1282.90  4378.1 1278.15
  4455.8 1274.39  4484.2 1271.77  4505.2 1273.73  4561.9 1273.04  4668.0 1277.78
  4781.5 1279.51  4901.7 1274.38  4936.9 1274.52  4958.5 1270.35  4993.6 1270.99
  5026.2 1269.66  5026.5 1266.66  5030.9 1266.66  5031.3 1269.66  5078.8 1274.23
  5142.3 1276.23  5156.5 1275.14  5199.1 1276.06  5227.5 1274.37  5297.8 1276.12
  5340.4 1274.19  5418.8 1276.13  5468.1 1279.11  5822.3 1292.13  5850.4 1292.30
#Mann=3,-1,0
  3816.4    0.05       0  5026.2    0.03       0  5031.3    0.05       0
Bank Sta=5026.2,5031.3
Exp/Cntr=0.3,0.1

Type RM Length L Ch R = 1,26000,500,500,500
BEGIN DESCRIPTION:
VASTERLING CREEK 52.0
END DESCRIPTION:
XS GIS Cut Line= 3
      2742006.69     10209197.62      2742855.98     10208676.93
      2743055.69     10207953.07
#Sta/Elev= 30
  4003.8 1282.83  4085.0 1281.75  4173.9 1278.36  4332.5 1275.87  4342.1 1276.91
  4347.9 1275.64  4369.2 1276.50  4384.7 1274.88  4552.9 1270.58  4601.3 1270.72
  4624.3 1268.45  4659.5 1274.68  4726.9 1276.28  4800.2 1275.43  4937.7 1271.55
  4964.9 1267.47  4980.3 1268.53  5010.8 1266.80  5011.2 1263.80  5015.6 1263.80
  5016.0 1266.80  5024.7 1268.78  5053.0 1270.14  5118.1 1268.91  5221.8 1278.21
  5279.9 1278.95  5359.0 1283.38  5546.3 1285.70  5580.7 1284.39  5750.9 1289.22
#Mann=3,-1,0
  4003.8    0.05       0  5010.8    0.05       0  5016.0    0.05       0
Bank Sta=5010.8,5016
Exp/Cntr=0.3,0.1

Type RM Length L Ch R = 1,25500,500,500,500
BEGIN DESCRIPTION:
VASTERLING CREEK 51.0
END DESCRIPTION:
XS GIS Cut Line= 3
      2741755.69     10209603.11      2743293.69     10208905.55
      2743955.66     10208503.12
#Sta/Elev= 30
  3311.2 1289.02  3475.9 1282.41  3788.7 1278.37  3964.9 1280.04  4277.5 1270.70
  4339.0 1265.46  4354.3 1268.49  4497.1 1268.19  4574.0 1273.62  4730.3 1268.46
  4897.4 1268.39  4995.7 1264.46  4996.1 1261.46  5000.5 1261.46  5001.0 1264.46
  5025.7 1265.94  5038.4 1270.46  5053.9 1272.22  5148.9 1271.87  5207.0 1277.10
  5338.7 1273.44  5439.5 1274.76  5455.0 1271.38  5513.1 1277.01  5528.6 1276.94
  5540.7 1274.04  5549.9 1276.73  5555.8 1274.59  5592.6 1278.62  5774.7 1286.11
#Mann=5,-1,0
  3311.2    0.05       0  3788.7    0.12       0  3964.9    0.05       0
  4995.7    0.05       0  5001.0    0.05       0
Bank Sta=4995.7,5001
Exp/Cntr=0.3,0.1

Type RM Length L Ch R = 1,25000,500,500,500
BEGIN DESCRIPTION:
VASTERLING CREEK 50.0
END DESCRIPTION:
XS GIS Cut Line= 3
      2742382.14     10209550.46      2743528.70     10209309.53
      2744147.00     10209197.86
#Sta/Elev= 30
  3828.4 1275.83  3855.0 1275.57  3956.9 1275.21  4376.7 1269.60  4455.3 1266.33
  4471.3 1263.97  4496.2 1262.57  4521.2 1265.37  4620.9 1267.48  4665.7 1265.70
  4771.6 1266.68  4815.2 1267.20  4958.8 1264.42  4975.2 1262.74  5002.3 1261.96
  5002.7 1258.96  5007.2 1258.96  5007.6 1261.96  5063.6 1264.36  5117.1 1264.43
  5139.2 1269.43  5169.7 1274.21  5180.8 1273.78  5220.5 1276.18  5240.8 1275.17
  5305.1 1276.52  5346.5 1276.29  5362.8 1277.91  5458.7 1279.92  5628.3 1279.15
#Mann=9,-1,0
  3828.4    0.05       0  3855.0    0.12       0  3956.9    0.05       0
  4771.6    0.12       0  4958.8    0.05       0  4975.2    0.12       0
  5002.3    0.07       0  5007.6    0.12       0  5305.1    0.05       0
Bank Sta=5002.3,5007.6
Exp/Cntr=0.3,0.1

Type RM Length L Ch R = 1,24500,500,500,500
BEGIN DESCRIPTION:
VASTERLING CREEK 49.0
END DESCRIPTION:
XS GIS Cut Line= 3
      2742602.87     10209897.40      2743434.41     10209709.98
      2744029.37     10209544.64
#Sta/Elev= 30
  4147.6 1277.97  4181.2 1278.19  4273.5 1276.93  4506.2 1271.52  4829.4 1262.95
  4867.5 1262.93  4878.3 1263.53  4909.0 1263.06  4929.5 1264.08  4950.0 1263.65
  4959.1 1262.33  4964.2 1262.78  4967.6 1259.62  4968.1 1256.62  4973.1 1256.62
  4973.6 1259.62  4991.1 1259.99  4998.1 1260.94  5046.2 1261.65  5085.6 1263.53
  5105.1 1263.14  5154.1 1264.08  5167.4 1264.95  5177.8 1264.68  5198.7 1265.79
  5340.9 1269.78  5499.5 1272.00  5527.7 1271.58  5532.8 1272.33  5617.5 1272.27
#Mann=3,-1,0
  4147.6    0.05       0  4967.6    0.03       0  4973.6    0.05       0
Bank Sta=4967.6,4973.6
Exp/Cntr=0.3,0.1

Type RM Length L Ch R = 1,24000,500,500,500
BEGIN DESCRIPTION:
VASTERLING CREEK 48.0
END DESCRIPTION:
XS GIS Cut Line= 3
      2742883.92     10210017.43      2743397.22     10210202.68
      2744029.41     10209842.08
#Sta/Elev= 30
  4454.3 1274.77  4693.7 1268.92  4860.2 1262.81  4892.1 1260.78  4897.8 1259.59
  4934.6 1257.95  4959.1 1257.77  4966.5 1258.60  4984.5 1257.30  5009.4 1256.56
  5009.9 1253.56  5014.9 1253.56  5015.4 1256.56  5021.3 1258.12  5034.0 1258.47
  5055.8 1260.26  5114.6 1260.74  5124.7 1260.17  5197.5 1260.96  5297.6 1261.24
  5329.1 1261.95  5366.6 1263.31  5372.5 1264.18  5431.5 1266.84  5474.7 1268.04
  5533.8 1267.79  5539.5 1268.26  5549.6 1267.44  5598.6 1267.67  5727.8 1266.13
#Mann=5,-1,0
  4454.3    0.05       0  5009.4    0.03       0  5015.4    0.05       0
  5197.5    0.12       0  5329.1    0.05       0
Bank Sta=5009.4,5015.4
Exp/Cntr=0.3,0.1