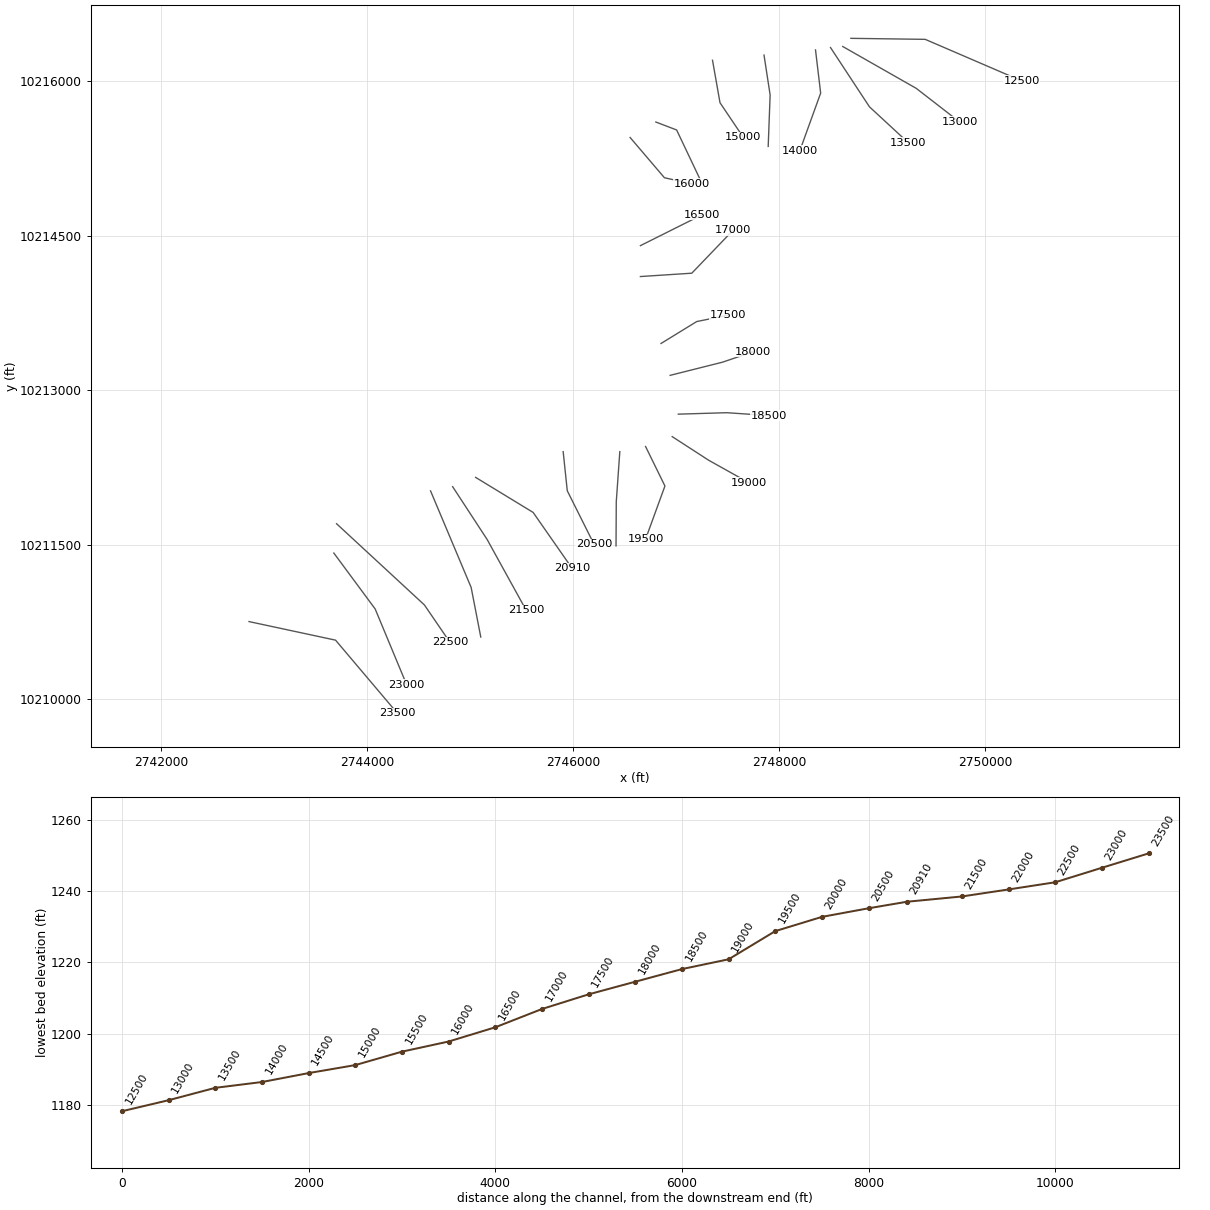
HEC-RAS study VASTERLING CREEK.prj: VASTERLING CREEK Base Level Engineering

--- VASTERLING CREEK.g01 (geometry) --- (continued)

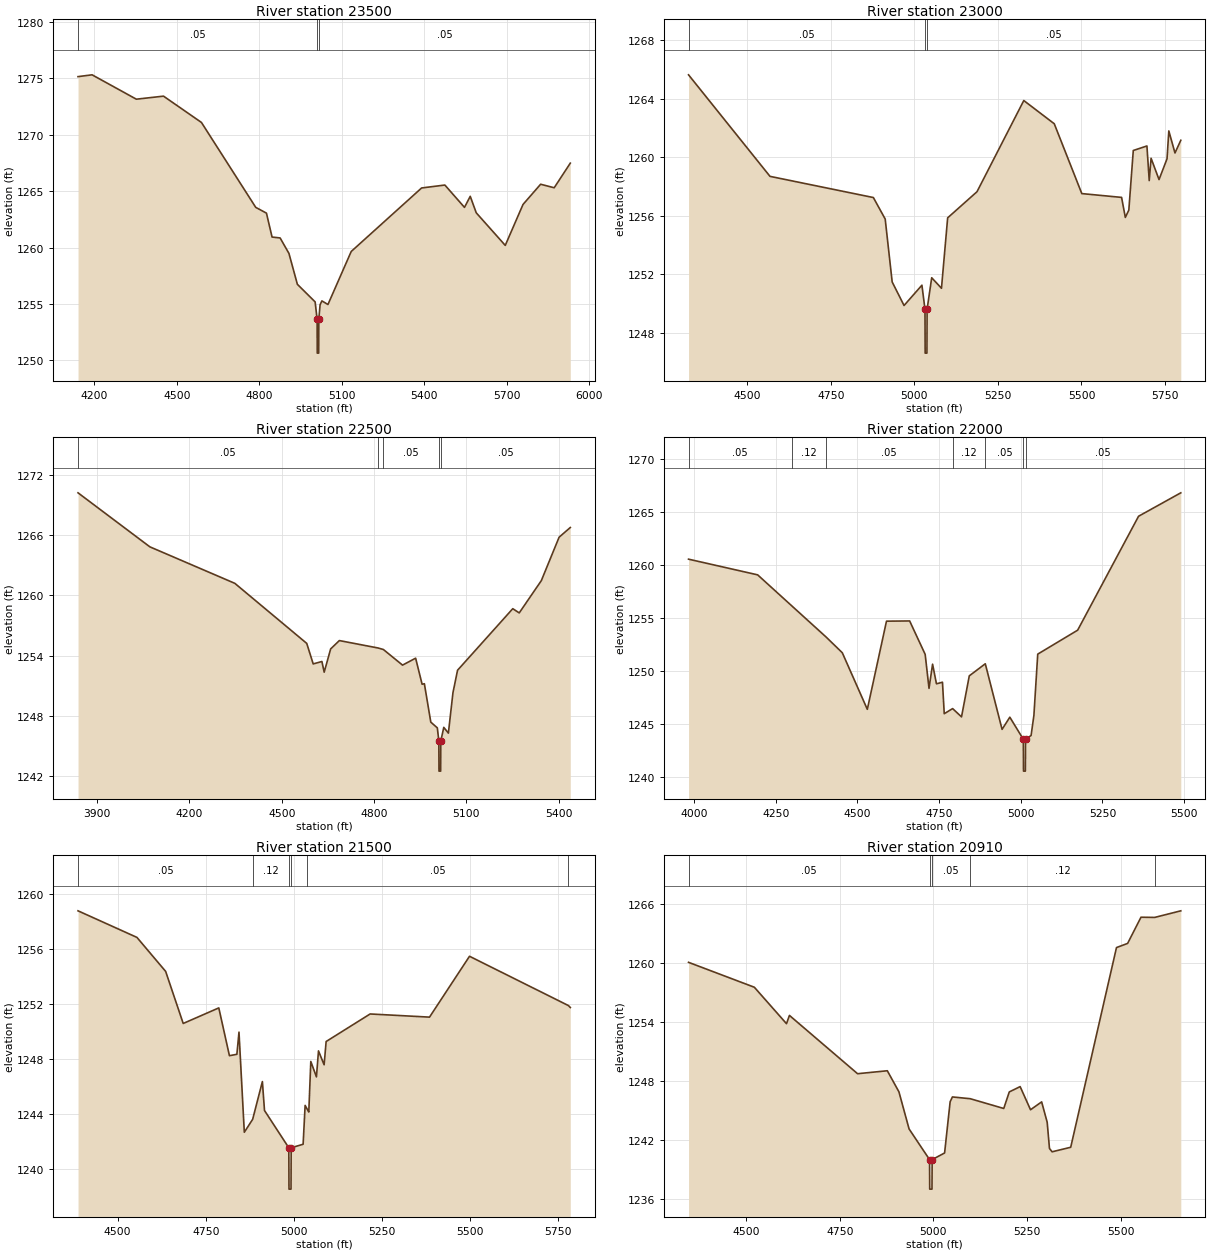
Type RM Length L Ch R = 1,23500,500,500,500
BEGIN DESCRIPTION:
VASTERLING CREEK 47.0
END DESCRIPTION:
XS GIS Cut Line= 3
      2742855.65     10210753.12      2743695.82     10210572.79
      2744297.12     10209861.89
#Sta/Elev= 30
  4140.7 1275.15  4191.9 1275.31  4352.8 1273.15  4451.6 1273.42  4589.5 1271.09
  4787.1 1263.56  4826.0 1263.05  4846.4 1260.93  4875.7 1260.85  4907.8 1259.48
  4938.5 1256.74  5003.1 1255.18  5010.3 1253.64  5010.8 1250.64  5016.0 1250.64
  5016.5 1253.64  5021.1 1254.93  5027.7 1255.27  5049.7 1254.95  5134.3 1259.65
  5390.3 1265.28  5474.9 1265.54  5546.3 1263.56  5567.2 1264.54  5589.0 1263.08
  5694.6 1260.19  5759.2 1263.82  5823.2 1265.61  5872.6 1265.30  5931.1 1267.48
#Mann=3,-1,0
  4140.7    0.05       0  5010.3    0.03       0  5016.5    0.05       0
Bank Sta=5010.3,5016.5
Exp/Cntr=0.3,0.1

Type RM Length L Ch R = 1,23000,500,500,500
BEGIN DESCRIPTION:
VASTERLING CREEK 46.0
END DESCRIPTION:
XS GIS Cut Line= 3
      2743679.15     10211418.44      2744080.45     10210875.56
      2744386.32     10210139.59
#Sta/Elev= 30
  4324.9 1265.65  4568.5 1258.70  4877.6 1257.25  4913.0 1255.78  4933.9 1251.47
  4969.4 1249.86  5022.8 1251.25  5032.0 1249.60  5032.5 1246.60  5037.8 1246.60
  5038.3 1249.60  5052.1 1251.76  5081.3 1251.04  5099.8 1255.86  5187.6 1257.65
  5327.5 1263.89  5418.6 1262.30  5501.0 1257.52  5619.9 1257.26  5631.1 1255.89
  5641.6 1256.39  5654.9 1260.47  5695.7 1260.78  5702.6 1258.41  5708.1 1259.94
  5731.9 1258.48  5755.8 1259.90  5761.2 1261.81  5779.6 1260.30  5797.0 1261.17
#Mann=3,-1,0
  4324.9    0.05       0  5032.0    0.03       0  5038.3    0.05       0
Bank Sta=5032,5038.3
Exp/Cntr=0.3,0.1

Type RM Length L Ch R = 1,22500,500,500,500
BEGIN DESCRIPTION:
VASTERLING CREEK 45.0
END DESCRIPTION:
XS GIS Cut Line= 3
      2743705.65     10211703.14      2744558.62     10210914.47
      2744805.66     10210553.15
#Sta/Elev= 30
  3838.3 1270.20  4071.7 1264.83  4347.8 1261.20  4581.4 1255.23  4602.4 1253.19
  4630.7 1253.43  4638.1 1252.37  4659.1 1254.68  4687.4 1255.51  4813.6 1254.77
  4830.5 1254.62  4892.7 1253.07  4935.2 1253.76  4956.2 1251.17  4963.6 1251.22
  4984.5 1247.40  5005.7 1246.83  5010.6 1245.53  5011.1 1242.53  5016.5 1242.53
  5017.0 1245.53  5026.7 1246.88  5041.6 1246.31  5056.5 1250.33  5071.4 1252.56
  5250.8 1258.68  5271.8 1258.26  5343.6 1261.47  5401.4 1265.79  5437.7 1266.75
#Mann=5,-1,0
  3838.3    0.05       0  4813.6    0.12       0  4830.5    0.05       0
  5010.6    0.03       0  5017.0    0.05       0
Bank Sta=5010.6,5017
Exp/Cntr=0.3,0.1

Type RM Length L Ch R = 1,22000,500,500,500
BEGIN DESCRIPTION:
VASTERLING CREEK 44.0
END DESCRIPTION:
XS GIS Cut Line= 3
      2744618.17     10212021.88      2745012.36     10211084.17
      2745105.68     10210603.14
#Sta/Elev= 30
  3982.8 1260.51  4194.4 1259.03  4298.7 1256.11  4403.4 1253.18  4453.6 1251.68
  4530.2 1246.34  4588.9 1254.66  4659.8 1254.68  4707.3 1251.53  4719.1 1248.32
  4730.0 1250.60  4741.9 1248.75  4760.3 1248.90  4765.7 1245.93  4791.4 1246.41
  4818.6 1245.63  4842.4 1249.50  4891.4 1250.64  4942.8 1244.45  4966.5 1245.60
  5007.9 1243.51  5008.4 1240.51  5014.1 1240.51  5014.6 1243.51  5031.6 1243.87
  5040.2 1245.76  5052.0 1251.55  5174.2 1253.81  5360.7 1264.56  5490.0 1266.77
#Mann=7,-1,0
  3982.8    0.05       0  4298.7    0.12       0  4403.4    0.05       0
  4791.4    0.12       0  4891.4    0.05       0  5007.9    0.03       0
  5014.6    0.05       0
Bank Sta=5007.9,5014.6
Exp/Cntr=0.3,0.1

Type RM Length L Ch R = 1,21500,590,590,590
BEGIN DESCRIPTION:
VASTERLING CREEK 43.0
END DESCRIPTION:
XS GIS Cut Line= 3
      2744832.54     10212063.05      2745167.37     10211550.41
      2745546.41     10210863.33
#Sta/Elev= 30
  4387.7 1258.75  4554.9 1256.82  4636.4 1254.35  4686.2 1250.57  4787.2 1251.70
  4817.4 1248.23  4838.5 1248.33  4844.5 1249.94  4859.6 1242.67  4883.3 1243.61
  4910.9 1246.35  4916.9 1244.25  4985.9 1241.54  4986.4 1238.54  4992.1 1238.54
  4992.6 1241.54  5026.5 1241.80  5032.2 1244.62  5038.4 1244.33  5042.6 1244.14
  5048.3 1247.81  5064.3 1246.69  5070.1 1248.58  5086.1 1247.57  5091.8 1249.26
  5216.7 1251.26  5385.2 1251.03  5498.7 1255.45  5779.4 1251.87  5784.7 1251.73
#Mann=6,-1,0
  4387.7    0.05       0  4883.3    0.12       0  4985.9    0.07       0
  4992.6    0.12       0  5038.4    0.05       0  5779.4    0.12       0
Bank Sta=4985.9,4992.6
Exp/Cntr=0.3,0.1

Type RM Length L Ch R = 1,20910,410,410,410
BEGIN DESCRIPTION:
VASTERLING CREEK 42.0
END DESCRIPTION:
XS GIS Cut Line= 3
      2745055.64     10212153.14      2745614.00     10211813.00
      2745991.64     10211271.23
#Sta/Elev= 30
  4346.2 1260.08  4521.9 1257.55  4607.7 1253.85  4615.6 1254.69  4797.5 1248.77
  4876.9 1249.07  4907.9 1246.93  4935.0 1243.16  4989.6 1240.05  4990.1 1237.05
  4996.1 1237.05  4996.6 1240.05  5029.8 1240.72  5044.6 1245.92  5050.7 1246.41
  5098.4 1246.23  5187.7 1245.24  5202.5 1246.92  5231.5 1247.46  5259.2 1245.11
  5288.9 1245.91  5303.7 1243.84  5309.8 1241.18  5316.8 1240.84  5366.5 1241.30
  5488.7 1261.58  5518.4 1262.00  5554.1 1264.66  5590.7 1264.64  5660.4 1265.31
#Mann=5,-1,0
  4346.2    0.05       0  4989.6    0.03       0  4996.6    0.05       0
  5098.4    0.12       0  5590.7    0.05       0
Bank Sta=4989.6,4996.6
Exp/Cntr=0.3,0.1

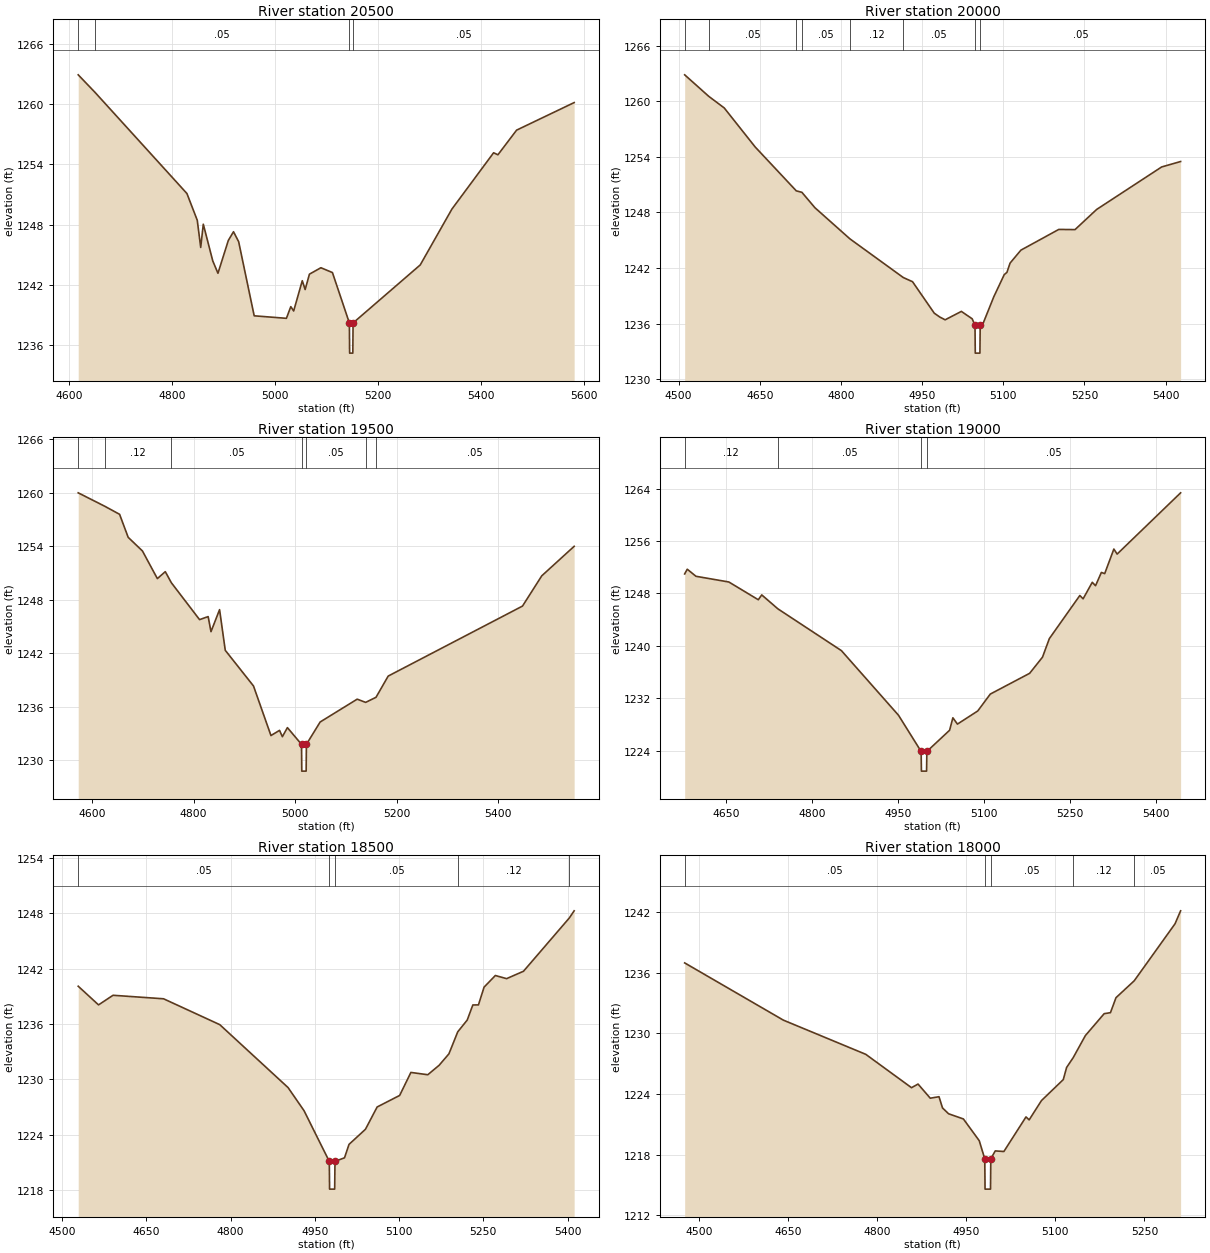
Type RM Length L Ch R = 1,20500,500,500,500
BEGIN DESCRIPTION:
VASTERLING CREEK 41.0
END DESCRIPTION:
XS GIS Cut Line= 3
      2745905.68     10212403.12      2745945.55     10212023.10
      2746205.67     10211503.14
#Sta/Elev= 30
  4617.9 1262.89  4650.3 1261.16  4829.1 1251.09  4849.2 1248.43  4855.9 1245.73
  4860.9 1248.04  4879.3 1244.39  4889.4 1243.16  4909.5 1246.42  4919.6 1247.29
  4929.6 1246.30  4959.8 1238.93  5022.4 1238.68  5030.9 1239.84  5036.5 1239.41
  5053.2 1242.42  5058.8 1241.54  5067.1 1243.07  5089.4 1243.71  5111.8 1243.23
  5144.7 1238.22  5145.2 1235.22  5151.4 1235.22  5151.9 1238.22  5282.4 1243.99
  5343.9 1249.54  5424.9 1255.14  5433.3 1254.94  5469.6 1257.39  5581.4 1260.13
#Mann=4,-1,0
  4617.9    0.12       0  4650.3    0.05       0  5144.7    0.03       0
  5151.9    0.05       0
Bank Sta=5144.7,5151.9
Exp/Cntr=0.3,0.1

Type RM Length L Ch R = 1,20000,500,500,500
BEGIN DESCRIPTION:
VASTERLING CREEK 40.0
END DESCRIPTION:
XS GIS Cut Line= 3
      2746455.68     10212403.09      2746421.26     10211915.70
      2746418.93     10211488.01
#Sta/Elev= 30
  4511.4 1262.88  4556.0 1260.55  4584.5 1259.30  4641.7 1255.08  4717.6 1250.34
  4728.0 1250.18  4752.0 1248.52  4816.5 1245.16  4915.3 1240.97  4932.4 1240.52
  4972.5 1237.12  4982.5 1236.71  4992.6 1236.40  5022.6 1237.31  5042.6 1236.51
  5047.8 1235.80  5048.3 1232.80  5056.9 1232.80  5057.4 1235.80  5062.6 1235.99
  5082.6 1238.90  5101.8 1241.28  5106.8 1241.53  5112.6 1242.53  5132.6 1243.93
  5202.6 1246.17  5232.6 1246.15  5272.6 1248.33  5392.6 1252.92  5427.7 1253.51
#Mann=8,-1,0
  4511.4    0.12       0  4556.0    0.05       0  4717.6    0.12       0
  4728.0    0.05       0  4816.5    0.12       0  4915.3    0.05       0
  5047.8    0.03       0  5057.4    0.05       0
Bank Sta=5047.8,5057.4
Exp/Cntr=0.3,0.1

Type RM Length L Ch R = 1,19500,500,500,500
BEGIN DESCRIPTION:
VASTERLING CREEK 39.0
END DESCRIPTION:
XS GIS Cut Line= 3
      2746705.70     10212453.08      2746893.72     10212069.37
      2746705.70     10211553.14
#Sta/Elev= 30
  4572.7 1260.01  4624.8 1258.51  4654.2 1257.60  4671.1 1255.02  4699.2 1253.49
  4728.6 1250.39  4744.2 1251.17  4756.1 1249.93  4811.7 1245.79  4828.6 1246.13
  4834.2 1244.44  4851.1 1246.91  4862.3 1242.35  4917.9 1238.35  4952.3 1232.79
  4969.2 1233.37  4974.8 1232.66  4984.7 1233.68  5012.5 1231.80  5013.0 1228.80
  5021.6 1228.80  5022.1 1231.80  5049.2 1234.31  5122.1 1236.87  5138.8 1236.51
  5159.2 1237.08  5183.2 1239.46  5447.7 1247.31  5485.6 1250.70  5549.4 1254.01
#Mann=7,-1,0
  4572.7    0.05       0  4624.8    0.12       0  4756.1    0.05       0
  5012.5    0.03       0  5022.1    0.05       0  5138.8    0.12       0
  5159.2    0.05       0
Bank Sta=5012.5,5022.1
Exp/Cntr=0.3,0.1

Type RM Length L Ch R = 1,19000,500,500,500
BEGIN DESCRIPTION:
VASTERLING CREEK 38.0
END DESCRIPTION:
XS GIS Cut Line= 3
      2746964.28     10212548.91      2747319.08     10212319.14
      2747705.71     10212103.10
#Sta/Elev= 30
  4577.3 1250.98  4581.8 1251.70  4597.0 1250.62  4654.4 1249.75  4705.8 1247.04
  4711.8 1247.78  4740.0 1245.65  4850.9 1239.27  4950.5 1229.41  4990.0 1223.88
  4990.5 1220.88  4999.5 1220.88  5000.0 1223.88  5039.7 1227.12  5045.4 1229.02
  5053.4 1228.06  5088.8 1230.06  5110.7 1232.64  5179.4 1235.81  5201.8 1238.27
  5213.8 1241.11  5267.0 1247.69  5272.7 1247.18  5288.7 1249.70  5294.4 1249.18
  5304.6 1251.21  5310.4 1251.03  5326.4 1254.78  5332.1 1254.01  5442.9 1263.36
#Mann=4,-1,0
  4577.3    0.12       0  4740.0    0.05       0  4990.0    0.05       0
  5000.0    0.05       0
Bank Sta=4990,5000
Exp/Cntr=0.3,0.1

Type RM Length L Ch R = 1,18500,500,500,500
BEGIN DESCRIPTION:
VASTERLING CREEK 37.0
END DESCRIPTION:
XS GIS Cut Line= 3
      2747023.73     10212767.05      2747494.82     10212781.13
      2747905.66     10212753.11
#Sta/Elev= 30
  4528.7 1240.09  4564.9 1238.07  4590.7 1239.11  4680.7 1238.73  4780.8 1235.93
  4902.4 1229.12  4930.8 1226.62  4975.8 1221.13  4976.3 1218.13  4985.4 1218.13
  4985.9 1221.13  5002.9 1221.52  5010.9 1222.97  5040.2 1224.61  5061.0 1227.02
  5101.1 1228.27  5121.1 1230.76  5151.2 1230.51  5171.3 1231.53  5188.8 1232.77
  5204.5 1235.15  5221.4 1236.43  5231.4 1238.06  5241.4 1238.07  5251.4 1239.99
  5271.5 1241.25  5291.5 1240.91  5321.6 1241.71  5403.1 1247.47  5411.8 1248.25
#Mann=5,-1,0
  4528.7    0.05       0  4975.8    0.05       0  4985.9    0.05       0
  5204.5    0.12       0  5403.1    0.05       0
Bank Sta=4975.8,4985.9
Exp/Cntr=0.3,0.1

Type RM Length L Ch R = 1,18000,500,500,500
BEGIN DESCRIPTION:
VASTERLING CREEK 36.0
END DESCRIPTION:
XS GIS Cut Line= 3
      2746944.40     10213143.82      2747453.16     10213271.74
      2747747.60     10213371.89
#Sta/Elev= 30
  4475.4 1236.95  4641.7 1231.29  4780.5 1227.91  4857.6 1224.61  4868.6 1224.97
  4889.2 1223.57  4903.9 1223.72  4909.8 1222.61  4920.1 1222.03  4945.0 1221.52
  4971.7 1219.37  4981.0 1217.58  4981.5 1214.58  4990.7 1214.58  4991.2 1217.58
  4998.7 1218.36  5013.2 1218.30  5050.5 1221.72  5055.8 1221.43  5076.6 1223.34
  5113.3 1225.41  5118.9 1226.61  5130.1 1227.59  5150.5 1229.76  5182.2 1231.93
  5192.8 1232.03  5202.1 1233.51  5232.8 1235.18  5301.5 1240.81  5311.0 1242.10
#Mann=5,-1,0
  4475.4    0.05       0  4981.0    0.03       0  4991.2    0.05       0
  5130.1    0.12       0  5232.8    0.05       0
Bank Sta=4981,4991.2
Exp/Cntr=0.3,0.1

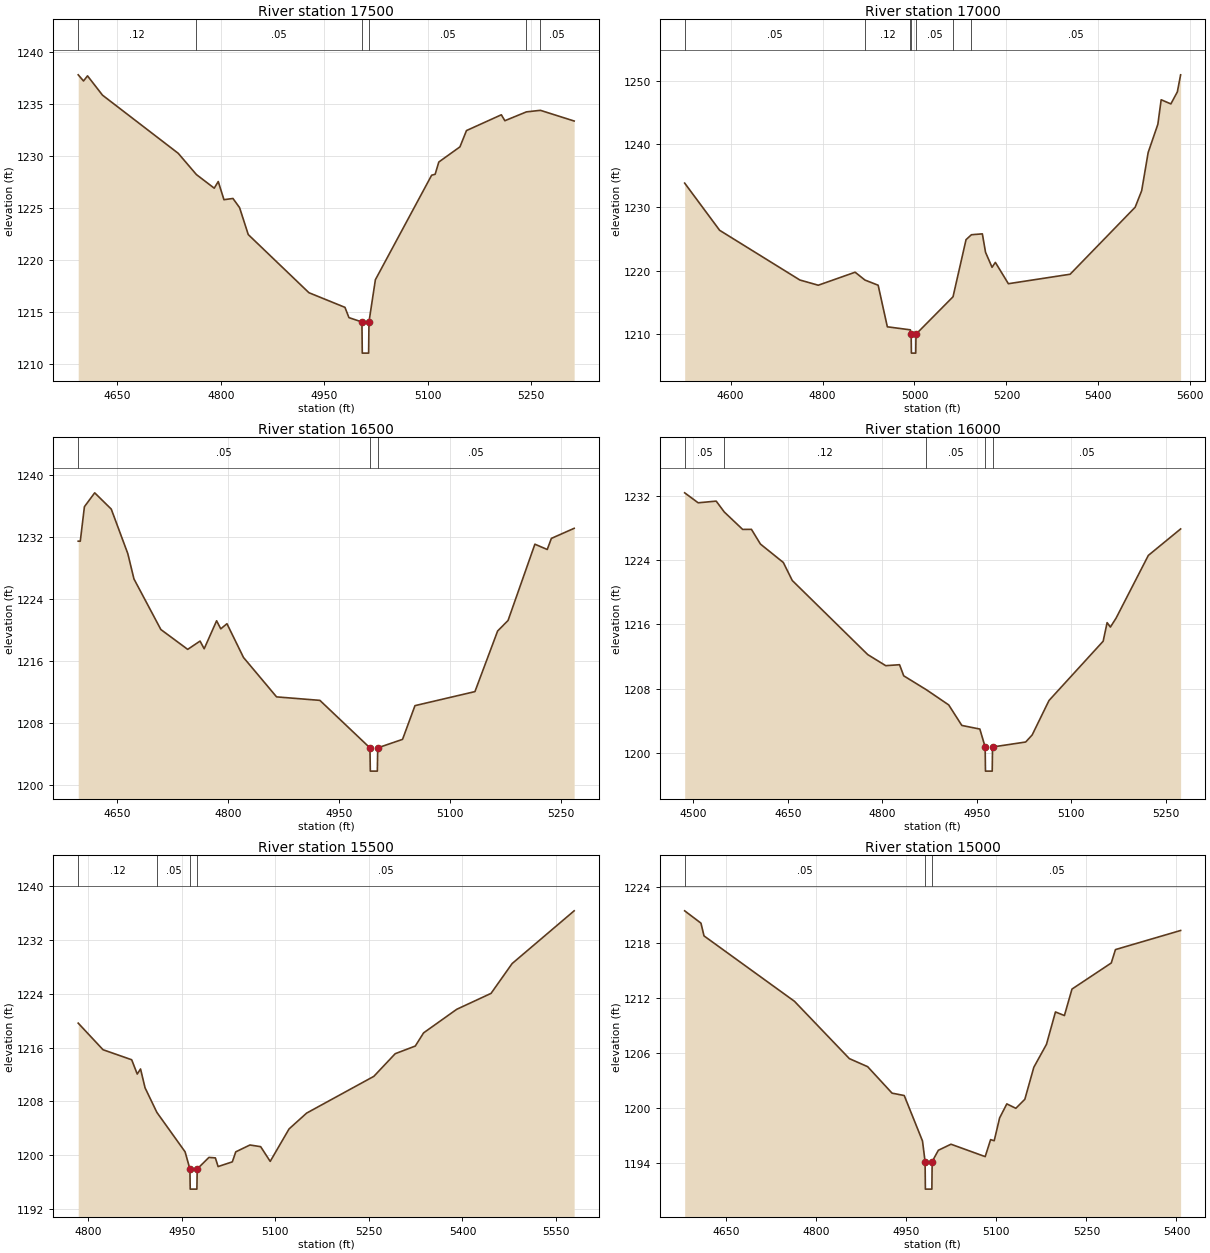
Type RM Length L Ch R = 1,17500,500,500,500
BEGIN DESCRIPTION:
VASTERLING CREEK 35.0
END DESCRIPTION:
XS GIS Cut Line= 3
      2746855.73     10213453.14      2747202.14     10213666.02
      2747507.83     10213728.46
#Sta/Elev= 30
  4593.4 1237.84  4601.1 1237.25  4606.9 1237.74  4628.6 1235.88  4738.3 1230.28
  4764.7 1228.23  4790.5 1226.92  4796.3 1227.56  4804.6 1225.81  4817.6 1225.93
  4827.2 1225.05  4839.8 1222.45  4927.7 1216.85  4979.9 1215.44  4985.7 1214.45
  5004.5 1214.03  5005.0 1211.03  5014.2 1211.03  5014.7 1214.03  5024.0 1218.10
  5105.5 1228.17  5110.6 1228.26  5115.9 1229.44  5146.5 1230.90  5156.0 1232.47
  5206.5 1233.99  5211.6 1233.42  5242.8 1234.27  5263.1 1234.42  5312.0 1233.39
#Mann=6,-1,0
  4593.4    0.12       0  4764.7    0.05       0  5004.5    0.03       0
  5014.7    0.05       0  5242.8    0.12       0  5263.1    0.05       0
Bank Sta=5004.5,5014.7
Exp/Cntr=0.3,0.1

Type RM Length L Ch R = 1,17000,500,500,500
BEGIN DESCRIPTION:
VASTERLING CREEK 34.0
END DESCRIPTION:
XS GIS Cut Line= 3
      2746655.69     10214103.11      2747154.54     10214135.57
      2747555.67     10214553.10
#Sta/Elev= 30
  4500.1 1233.85  4576.2 1226.37  4750.6 1218.50  4790.7 1217.67  4870.9 1219.73
  4892.3 1218.49  4921.0 1217.67  4941.0 1211.08  4991.0 1210.60  4992.8 1209.91
  4993.3 1206.91  5002.8 1206.91  5003.3 1209.91  5083.9 1215.84  5112.2 1224.89
  5123.9 1225.67  5147.7 1225.81  5154.6 1222.89  5168.8 1220.51  5176.0 1221.29
  5204.3 1217.91  5338.6 1219.41  5480.1 1230.03  5494.3 1232.65  5508.4 1238.70
  5529.5 1243.18  5536.7 1247.06  5557.8 1246.40  5571.9 1248.31  5579.0 1251.01
#Mann=7,-1,0
  4500.1    0.05       0  4892.3    0.12       0  4991.0    0.05       0
  4992.8    0.03       0  5003.3    0.05       0  5083.9    0.12       0
  5123.9    0.05       0
Bank Sta=4992.8,5003.3
Exp/Cntr=0.3,0.1

Type RM Length L Ch R = 1,16500,500,500,500
BEGIN DESCRIPTION:
VASTERLING CREEK 33.0
END DESCRIPTION:
XS GIS Cut Line= 3
      2746655.71     10214403.13      2747015.95     10214583.35
      2747255.69     10214703.12
#Sta/Elev= 30
  4597.2 1231.44  4600.0 1231.44  4605.6 1235.89  4619.5 1237.68  4641.9 1235.58
  4664.3 1229.83  4672.6 1226.57  4709.0 1220.04  4745.3 1217.48  4762.0 1218.55
  4767.6 1217.56  4784.4 1221.17  4790.0 1220.13  4798.4 1220.79  4820.8 1216.43
  4865.5 1211.35  4924.1 1210.90  4991.8 1204.77  4992.3 1201.77  5001.8 1201.77
  5002.3 1204.77  5035.9 1205.87  5052.7 1210.22  5133.8 1212.03  5164.5 1219.85
  5178.6 1221.21  5214.9 1231.05  5231.6 1230.37  5237.2 1231.80  5268.0 1233.10
#Mann=3,-1,0
  4597.2    0.05       0  4991.8    0.05       0  5002.3    0.05       0
Bank Sta=4991.8,5002.3
Exp/Cntr=0.3,0.1

Type RM Length L Ch R = 1,16000,500,500,500
BEGIN DESCRIPTION:
VASTERLING CREEK 32.0
END DESCRIPTION:
XS GIS Cut Line= 3
      2746555.69     10215453.10      2746888.83     10215062.33
      2747155.64     10215003.12
#Sta/Elev= 30
  4486.5 1232.37  4507.9 1231.13  4536.5 1231.34  4549.3 1229.99  4578.5 1227.82
  4592.4 1227.83  4606.7 1226.00  4643.0 1223.71  4657.2 1221.47  4776.9 1212.26
  4805.5 1210.88  4827.4 1211.00  4834.0 1209.62  4870.1 1207.88  4905.4 1206.00
  4926.2 1203.45  4954.8 1203.00  4963.2 1200.77  4963.7 1197.77  4974.4 1197.77
  4974.9 1200.77  5027.5 1201.39  5037.8 1202.27  5064.5 1206.55  5150.4 1213.92
  5156.7 1216.23  5161.9 1215.68  5170.9 1216.79  5222.1 1224.59  5273.3 1227.88
#Mann=5,-1,0
  4486.5    0.05       0  4549.3    0.12       0  4870.1    0.05       0
  4963.2    0.03       0  4974.9    0.05       0
Bank Sta=4963.2,4974.9
Exp/Cntr=0.3,0.1

Type RM Length L Ch R = 1,15500,500,500,500
BEGIN DESCRIPTION:
VASTERLING CREEK 31.0
END DESCRIPTION:
XS GIS Cut Line= 3
      2746805.65     10215603.13      2747007.25     10215526.16
      2747255.67     10215003.15
#Sta/Elev= 30
  4784.2 1219.63  4824.0 1215.67  4869.9 1214.18  4878.8 1212.05  4884.1 1212.81
  4891.3 1210.01  4910.3 1206.34  4955.5 1200.47  4963.2 1197.92  4963.7 1194.92
  4974.4 1194.92  4974.9 1197.92  4993.7 1199.64  5004.0 1199.57  5008.4 1198.28
  5031.2 1198.98  5036.7 1200.47  5059.4 1201.49  5076.6 1201.24  5091.9 1199.05
  5122.1 1203.88  5150.3 1206.24  5258.0 1211.71  5292.2 1215.08  5324.4 1216.22
  5337.7 1218.18  5390.8 1221.69  5445.8 1224.06  5479.6 1228.50  5579.0 1236.35
#Mann=4,-1,0
  4784.2    0.12       0  4910.3    0.05       0  4963.2    0.05       0
  4974.9    0.05       0
Bank Sta=4963.2,4974.9
Exp/Cntr=0.3,0.1

Type RM Length L Ch R = 1,15000,500,500,500
BEGIN DESCRIPTION:
VASTERLING CREEK 30.0
END DESCRIPTION:
XS GIS Cut Line= 3
      2747355.68     10216203.14      2747428.41     10215790.60
      2747655.69     10215453.10
#Sta/Elev= 30
  4581.1 1221.45  4608.2 1220.11  4613.3 1218.72  4763.9 1211.60  4855.3 1205.36
  4885.8 1204.48  4926.4 1201.60  4946.7 1201.34  4977.1 1196.39  4981.4 1194.15
  4981.9 1191.15  4992.7 1191.15  4993.2 1194.15  5003.5 1195.38  5024.5 1196.04
  5081.5 1194.69  5090.5 1196.54  5096.5 1196.42  5105.5 1198.90  5117.5 1200.43
  5132.5 1199.95  5147.5 1200.93  5162.5 1204.42  5183.5 1206.91  5198.5 1210.44
  5213.4 1210.05  5226.0 1212.93  5291.4 1215.77  5298.4 1217.23  5406.9 1219.31
#Mann=3,-1,0
  4581.1    0.05       0  4981.4    0.03       0  4993.2    0.05       0
Bank Sta=4981.4,4993.2
Exp/Cntr=0.3,0.1

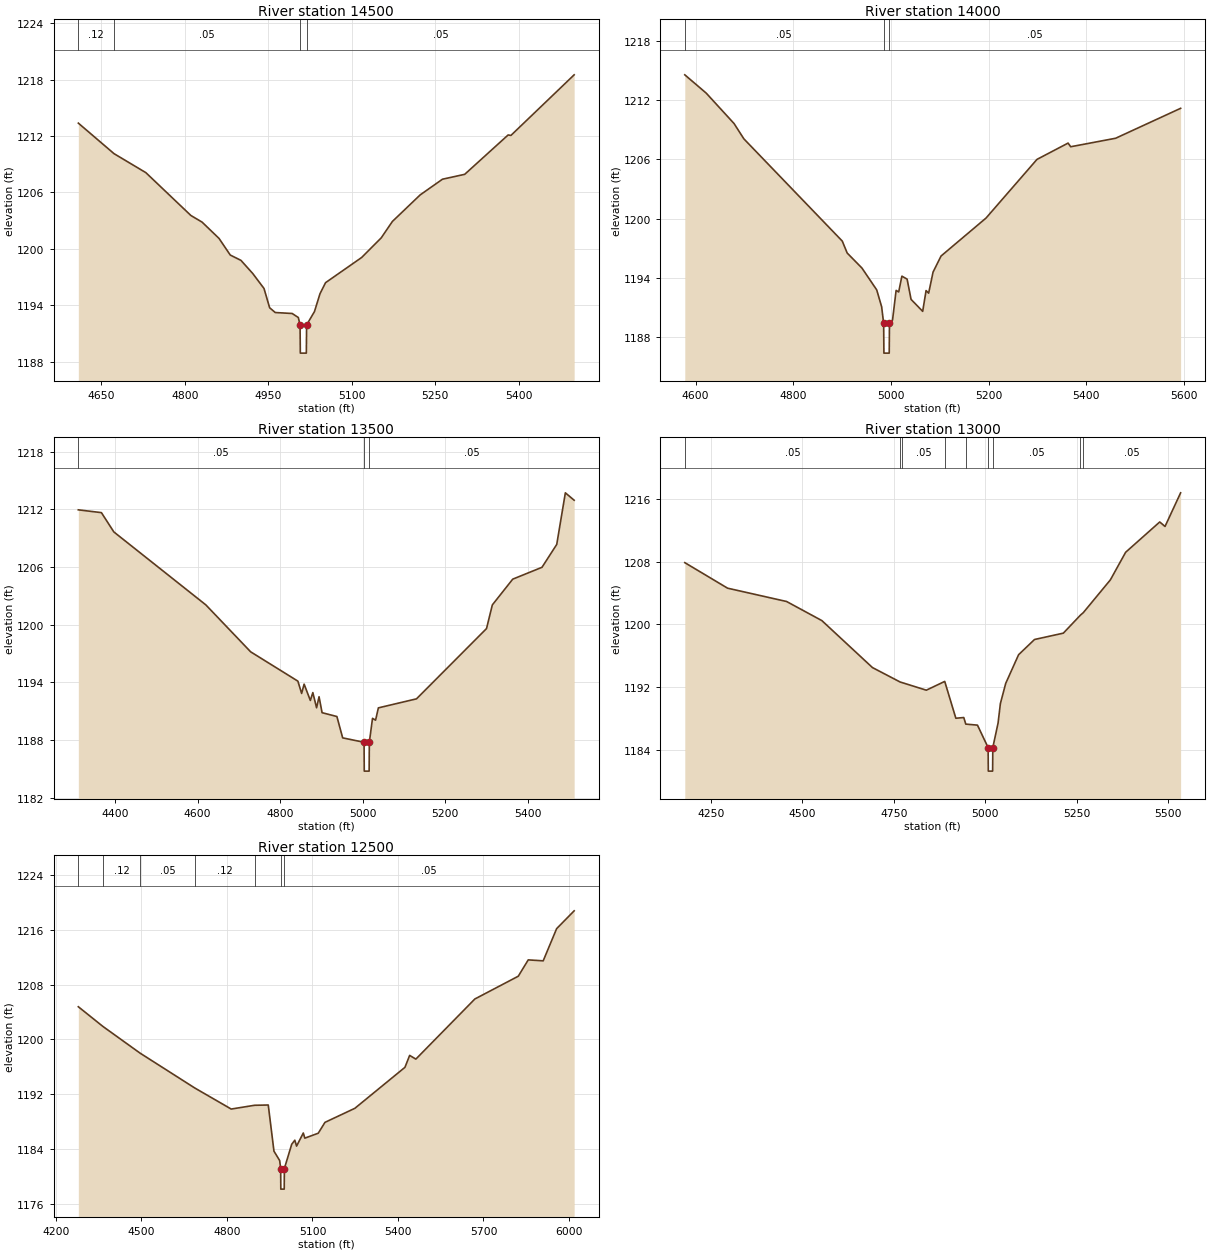
Type RM Length L Ch R = 1,14500,500,500,500
BEGIN DESCRIPTION:
VASTERLING CREEK 29.0
END DESCRIPTION:
XS GIS Cut Line= 3
      2747855.68     10216253.15      2747915.10     10215866.08
      2747896.35     10215366.43
#Sta/Elev= 30
  4608.4 1213.38  4672.6 1210.13  4729.8 1208.11  4810.8 1203.55  4831.0 1202.84
  4861.4 1201.11  4881.6 1199.34  4900.9 1198.77  4922.1 1197.37  4942.3 1195.78
  4952.4 1193.73  4962.5 1193.22  4992.9 1193.12  5004.0 1192.69  5007.1 1191.90
  5007.6 1188.90  5018.4 1188.90  5018.9 1191.90  5033.0 1193.32  5043.0 1195.23
  5053.0 1196.40  5117.9 1199.08  5153.1 1201.17  5173.1 1202.91  5223.1 1205.74
  5263.2 1207.41  5303.2 1207.93  5381.3 1212.12  5386.3 1212.07  5500.0 1218.52
#Mann=4,-1,0
  4608.4    0.12       0  4672.6    0.05       0  5007.1    0.03       0
  5018.9    0.05       0
Bank Sta=5007.1,5018.9
Exp/Cntr=0.3,0.1

Type RM Length L Ch R = 1,14000,500,500,500
BEGIN DESCRIPTION:
VASTERLING CREEK 28.0
END DESCRIPTION:
XS GIS Cut Line= 3
      2748355.68     10216303.16      2748405.63     10215884.12
      2748204.18     10215326.61
#Sta/Elev= 30
  4578.0 1214.56  4621.8 1212.71  4678.8 1209.63  4698.9 1208.08  4900.3 1197.73
  4910.4 1196.52  4940.6 1195.00  4970.8 1192.79  4980.9 1191.08  4985.0 1189.39
  4985.5 1186.39  4996.4 1186.39  4996.9 1189.39  5003.2 1189.75  5010.5 1192.74
  5015.8 1192.58  5022.3 1194.18  5033.0 1193.88  5041.1 1191.83  5064.9 1190.62
  5071.8 1192.72  5077.1 1192.46  5086.1 1194.59  5102.5 1196.22  5194.5 1200.06
  5298.8 1206.00  5362.5 1207.65  5367.8 1207.28  5459.8 1208.14  5592.8 1211.17
#Mann=3,-1,0
  4578.0    0.05       0  4985.0    0.03       0  4996.9    0.05       0
Bank Sta=4985,4996.9
Exp/Cntr=0.3,0.1

Type RM Length L Ch R = 1,13500,500,500,500
BEGIN DESCRIPTION:
VASTERLING CREEK 27.0
END DESCRIPTION:
XS GIS Cut Line= 3
      2748501.13     10216326.56      2748879.49     10215750.86
      2749255.68     10215403.11
#Sta/Elev= 30
  4311.1 1211.94  4367.0 1211.65  4397.2 1209.64  4620.1 1202.05  4728.6 1197.17
  4843.0 1194.12  4852.1 1192.84  4858.1 1193.81  4873.2 1192.11  4879.2 1192.93
  4888.3 1191.35  4894.3 1192.50  4901.6 1190.84  4937.5 1190.44  4951.5 1188.22
  5003.3 1187.76  5003.8 1184.76  5015.6 1184.76  5016.1 1187.76  5023.8 1190.25
  5031.2 1190.06  5038.0 1191.34  5130.4 1192.28  5300.0 1199.59  5314.1 1202.05
  5363.5 1204.73  5434.3 1205.96  5470.1 1208.34  5491.0 1213.71  5512.3 1212.94
#Mann=3,-1,0
  4311.1    0.05       0  5003.3    0.03       0  5016.1    0.05       0
Bank Sta=5003.3,5016.1
Exp/Cntr=0.3,0.1

Type RM Length L Ch R = 1,13000,500,500,500
BEGIN DESCRIPTION:
VASTERLING CREEK 26.0
END DESCRIPTION:
XS GIS Cut Line= 3
      2748620.10     10216336.49      2749333.52     10215930.20
      2749755.72     10215603.08
#Sta/Elev= 30
  4179.0 1207.89  4295.9 1204.63  4457.2 1202.93  4553.7 1200.49  4691.8 1194.50
  4767.7 1192.65  4772.8 1192.58  4839.1 1191.61  4889.4 1192.73  4919.8 1188.03
  4941.4 1188.12  4947.0 1187.28  4978.9 1187.15  5008.0 1184.28  5008.5 1181.28
  5020.3 1181.28  5020.8 1184.28  5035.2 1187.42  5041.5 1189.90  5056.0 1192.47
  5091.3 1196.14  5134.8 1198.08  5213.6 1198.89  5260.3 1201.19  5268.0 1201.50
  5342.1 1205.69  5383.8 1209.21  5477.0 1213.08  5491.5 1212.51  5534.1 1216.80
#Mann=9,-1,0
  4179.0    0.05       0  4767.7    0.12       0  4772.8    0.05       0
  4889.4    0.12       0  4947.0    0.05       0  5008.0    0.03       0
  5020.8    0.05       0  5260.3    0.12       0  5268.0    0.05       0
Bank Sta=5008,5020.8
Exp/Cntr=0.3,0.1

Type RM Length L Ch R = 1,12500,500,500,500
BEGIN DESCRIPTION:
VASTERLING CREEK 25.0
END DESCRIPTION:
XS GIS Cut Line= 3
      2748699.46     10216415.82      2749420.69     10216405.99
      2750355.68     10216003.11
#Sta/Elev= 30
  4278.7 1204.76  4364.6 1201.90  4495.3 1198.00  4686.8 1192.93  4815.0 1189.85
  4897.0 1190.40  4945.0 1190.44  4965.0 1183.71  4985.0 1182.35  4988.5 1181.18
  4989.0 1178.18  5001.0 1178.18  5001.5 1181.18  5027.2 1184.71  5038.1 1185.31
  5044.4 1184.45  5067.9 1186.36  5073.3 1185.61  5120.4 1186.33  5143.9 1187.91
  5248.9 1189.96  5424.5 1195.93  5441.0 1197.67  5462.8 1197.13  5669.7 1205.89
  5822.1 1209.21  5857.0 1211.59  5909.5 1211.45  5956.6 1216.14  6018.1 1218.74
#Mann=7,-1,0
  4278.7    0.05       0  4364.6    0.12       0  4495.3    0.05       0
  4686.8    0.12       0  4897.0    0.05       0  4988.5    0.03       0
  5001.5    0.05       0
Bank Sta=4988.5,5001.5
Exp/Cntr=0.3,0.1