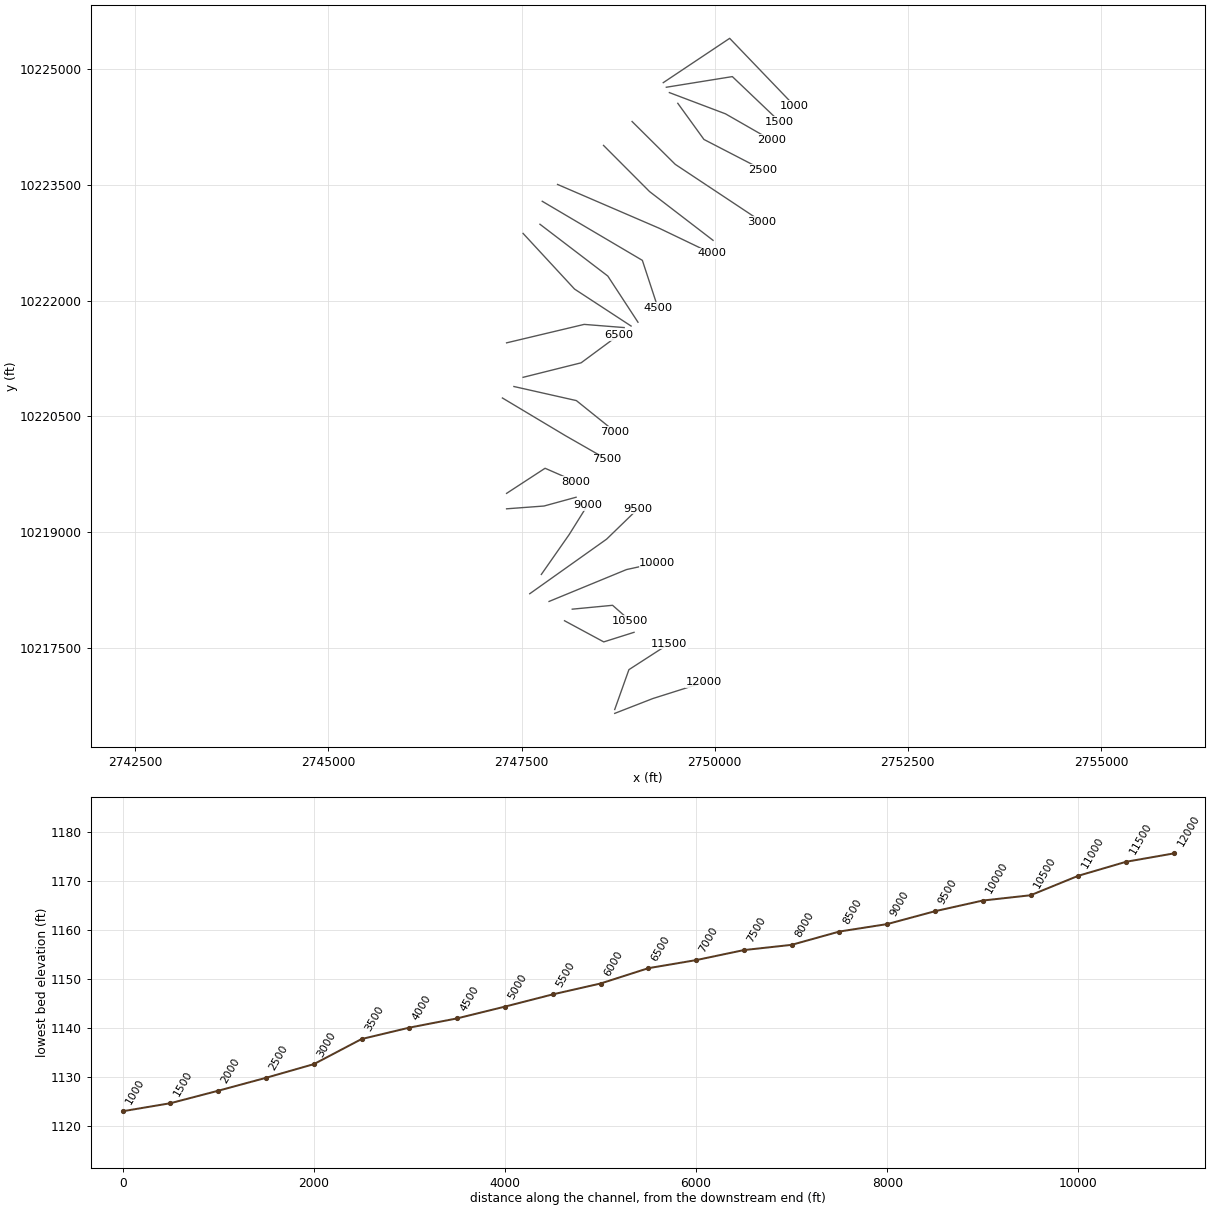
HEC-RAS study VASTERLING CREEK.prj: VASTERLING CREEK Base Level Engineering

--- VASTERLING CREEK.g01 (geometry) --- (continued)

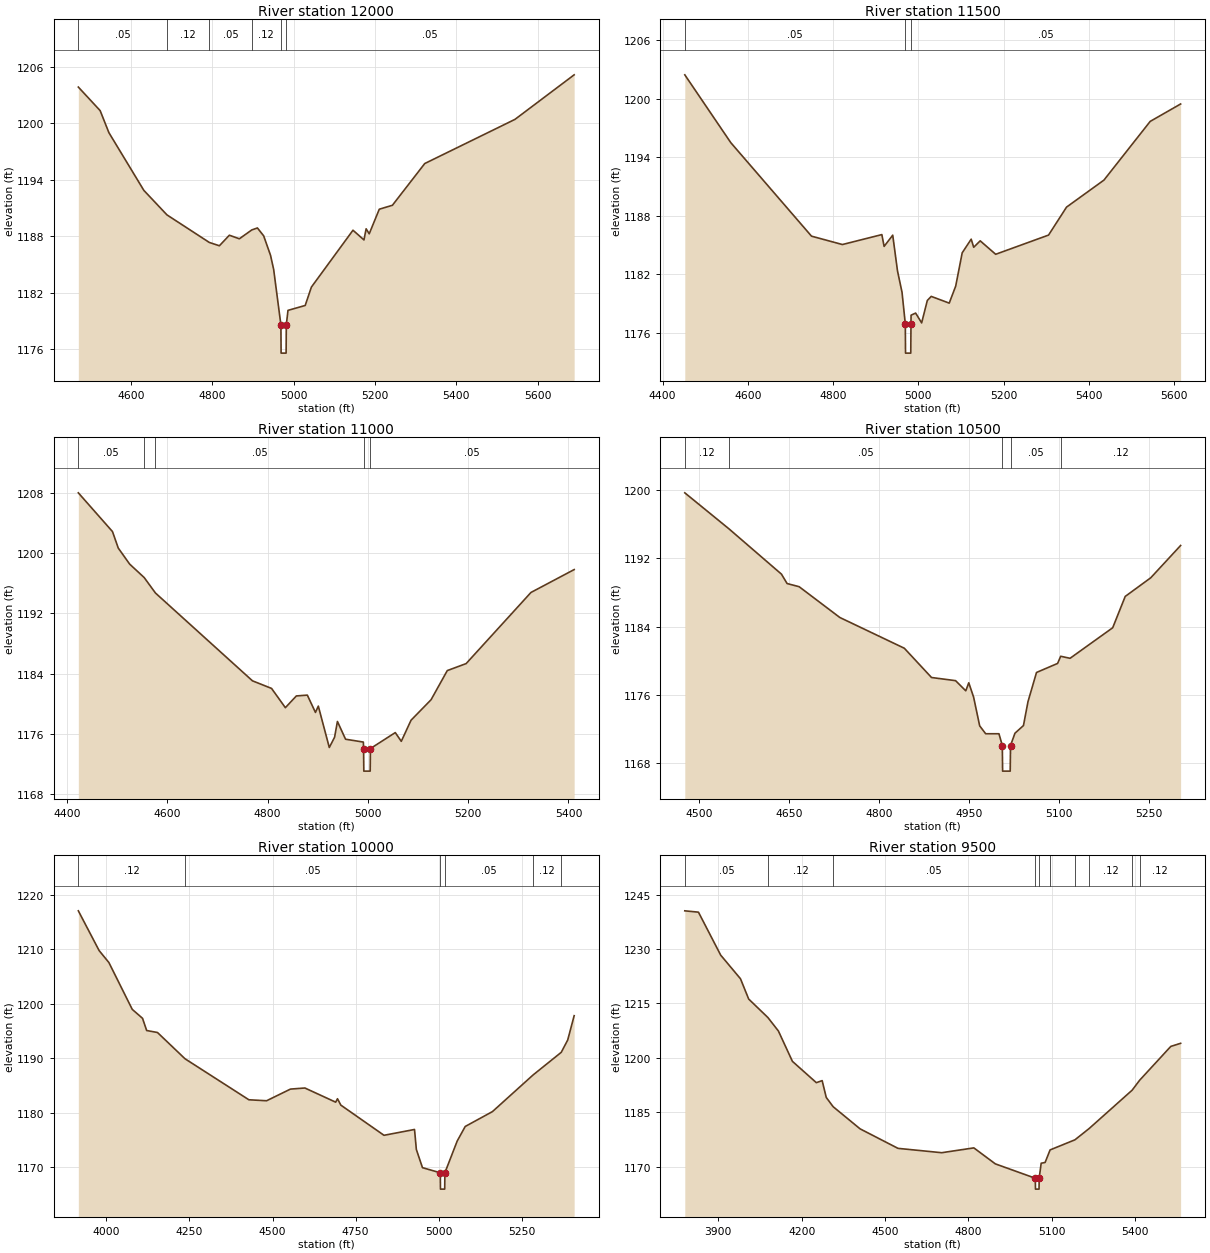
Type RM Length L Ch R = 1,12000,500,500,500
BEGIN DESCRIPTION:
VASTERLING CREEK 24.0
END DESCRIPTION:
XS GIS Cut Line= 3
      2748705.70     10216653.12      2749198.54     10216845.07
      2749855.69     10217053.11
#Sta/Elev= 30
  4471.1 1203.86  4524.7 1201.36  4546.2 1199.02  4632.1 1192.89  4688.8 1190.29
  4793.0 1187.36  4817.7 1187.01  4842.2 1188.13  4866.7 1187.75  4897.2 1188.69
  4911.1 1188.90  4926.5 1188.06  4943.3 1186.00  4951.0 1184.50  4968.8 1178.61
  4969.3 1175.61  4981.6 1175.61  4982.1 1178.61  4986.2 1180.15  5028.5 1180.67
  5043.7 1182.62  5145.9 1188.66  5172.9 1187.63  5178.2 1188.81  5185.8 1188.28
  5210.5 1190.89  5242.8 1191.31  5322.2 1195.74  5543.9 1200.43  5689.3 1205.16
#Mann=6,-1,0
  4471.1    0.05       0  4688.8    0.12       0  4793.0    0.05       0
  4897.2    0.12       0  4968.8    0.05       0  4982.1    0.05       0
Bank Sta=4968.8,4982.1
Exp/Cntr=0.3,0.1

Type RM Length L Ch R = 1,11500,500,500,500
BEGIN DESCRIPTION:
VASTERLING CREEK 23.0
END DESCRIPTION:
XS GIS Cut Line= 3
      2748705.70     10216703.15      2748889.27     10217219.27
      2749405.66     10217553.10
#Sta/Elev= 30
  4452.2 1202.45  4560.1 1195.49  4749.3 1185.90  4821.8 1185.04  4914.3 1186.06
  4919.6 1184.85  4939.8 1186.00  4951.0 1182.33  4961.6 1180.14  4969.3 1176.90
  4969.8 1173.90  4982.1 1173.90  4982.6 1176.90  4982.8 1177.79  4993.5 1178.01
  5007.6 1177.00  5020.9 1179.30  5030.1 1179.72  5072.3 1179.03  5087.5 1180.78
  5102.7 1184.19  5123.8 1185.59  5129.7 1184.76  5144.9 1185.42  5181.2 1184.04
  5305.2 1186.01  5347.4 1188.88  5435.1 1191.65  5543.5 1197.67  5614.9 1199.46
#Mann=3,-1,0
  4452.2    0.05       0  4969.3    0.03       0  4982.6    0.05       0
Bank Sta=4969.3,4982.6
Exp/Cntr=0.3,0.1

Type RM Length L Ch R = 1,11000,500,500,500
BEGIN DESCRIPTION:
VASTERLING CREEK 22.0
END DESCRIPTION:
XS GIS Cut Line= 3
      2748055.66     10217853.13      2748563.56     10217579.11
      2748955.72     10217703.12
#Sta/Elev= 30
  4422.9 1208.02  4491.0 1202.87  4502.5 1200.68  4525.2 1198.55  4554.2 1196.76
  4576.6 1194.71  4770.0 1183.04  4808.1 1182.03  4835.6 1179.47  4857.5 1181.03
  4879.4 1181.14  4895.6 1178.84  4901.3 1179.68  4923.2 1174.18  4933.7 1175.54
  4939.4 1177.64  4955.6 1175.28  4991.1 1174.90  4991.5 1174.04  4992.0 1171.04
  5004.7 1171.04  5005.2 1174.04  5054.7 1176.16  5066.7 1175.00  5086.1 1177.80
  5126.1 1180.53  5158.4 1184.40  5196.0 1185.33  5325.2 1194.78  5411.3 1197.82
#Mann=5,-1,0
  4422.9    0.05       0  4554.2    0.12       0  4576.6    0.05       0
  4991.5    0.03       0  5005.2    0.05       0
Bank Sta=4991.5,5005.2
Exp/Cntr=0.3,0.1

Type RM Length L Ch R = 1,10500,500,500,500
BEGIN DESCRIPTION:
VASTERLING CREEK 21.0
END DESCRIPTION:
XS GIS Cut Line= 3
      2748155.67     10218003.11      2748677.77     10218053.22
      2748905.69     10217853.11
#Sta/Elev= 30
  4475.5 1199.67  4548.9 1195.47  4636.9 1190.14  4646.3 1189.04  4666.4 1188.67
  4734.4 1185.06  4842.0 1181.46  4887.4 1178.03  4927.6 1177.66  4944.6 1176.47
  4949.6 1177.41  4957.7 1175.73  4967.8 1172.37  4977.8 1171.44  5000.0 1171.44
  5005.6 1170.06  5006.1 1167.06  5018.8 1167.06  5019.3 1170.06  5026.7 1171.50
  5040.9 1172.40  5048.5 1175.21  5062.7 1178.62  5097.9 1179.68  5103.1 1180.52
  5118.7 1180.28  5189.9 1183.86  5210.8 1187.53  5253.5 1189.72  5303.3 1193.50
#Mann=5,-1,0
  4475.5    0.12       0  4548.9    0.05       0  5005.6    0.03       0
  5019.3    0.05       0  5103.1    0.12       0
Bank Sta=5005.6,5019.3
Exp/Cntr=0.3,0.1

Type RM Length L Ch R = 1,10000,500,500,500
BEGIN DESCRIPTION:
VASTERLING CREEK 20.0
END DESCRIPTION:
XS GIS Cut Line= 3
      2747855.66     10218103.10      2748858.06     10218515.98
      2749255.73     10218603.12
#Sta/Elev= 30
  3915.9 1217.06  3978.5 1209.76  4007.8 1207.57  4078.1 1198.97  4109.0 1197.33
  4121.4 1195.09  4153.9 1194.73  4236.7 1189.91  4428.8 1182.38  4482.1 1182.20
  4553.9 1184.34  4597.3 1184.54  4689.9 1181.94  4695.3 1182.57  4705.4 1181.40
  4835.2 1175.86  4927.0 1176.93  4932.5 1173.26  4950.9 1169.92  5004.5 1168.98
  5005.0 1165.98  5017.8 1165.98  5018.3 1168.98  5055.3 1174.80  5079.5 1177.48
  5161.4 1180.21  5283.3 1186.92  5368.3 1191.09  5387.7 1193.35  5407.1 1197.81
#Mann=6,-1,0
  3915.9    0.12       0  4236.7    0.05       0  5004.5    0.03       0
  5018.3    0.05       0  5283.3    0.12       0  5368.3    0.05       0
Bank Sta=5004.5,5018.3
Exp/Cntr=0.3,0.1

Type RM Length L Ch R = 1,9500,500,500,500
BEGIN DESCRIPTION:
VASTERLING CREEK 19.0
END DESCRIPTION:
XS GIS Cut Line= 3
      2747605.66     10218203.09      2748600.80     10218910.22
      2749005.70     10219303.13
#Sta/Elev= 30
  3779.2 1240.52  3828.4 1240.15  3908.4 1228.31  3979.7 1221.79  4009.2 1216.20
  4078.3 1211.11  4116.2 1207.39  4166.7 1199.02  4252.8 1193.15  4273.7 1193.71
  4288.4 1189.08  4313.3 1186.52  4410.2 1180.42  4546.7 1175.04  4704.1 1173.84
  4819.8 1175.17  4897.2 1170.76  5041.1 1166.80  5041.6 1163.80  5054.5 1163.80
  5055.0 1166.80  5062.2 1170.94  5076.3 1171.15  5094.3 1174.61  5183.9 1177.40
  5235.4 1180.54  5389.6 1191.07  5416.6 1193.81  5528.8 1203.14  5564.2 1204.00
#Mann=10,-1,0
  3779.2    0.05       0  4078.3    0.12       0  4313.3    0.05       0
  5041.1    0.03       0  5055.0    0.05       0  5094.3    0.12       0
  5183.9    0.05       0  5235.4    0.12       0  5389.6    0.05       0
  5416.6    0.12       0
Bank Sta=5041.1,5055
Exp/Cntr=0.3,0.1

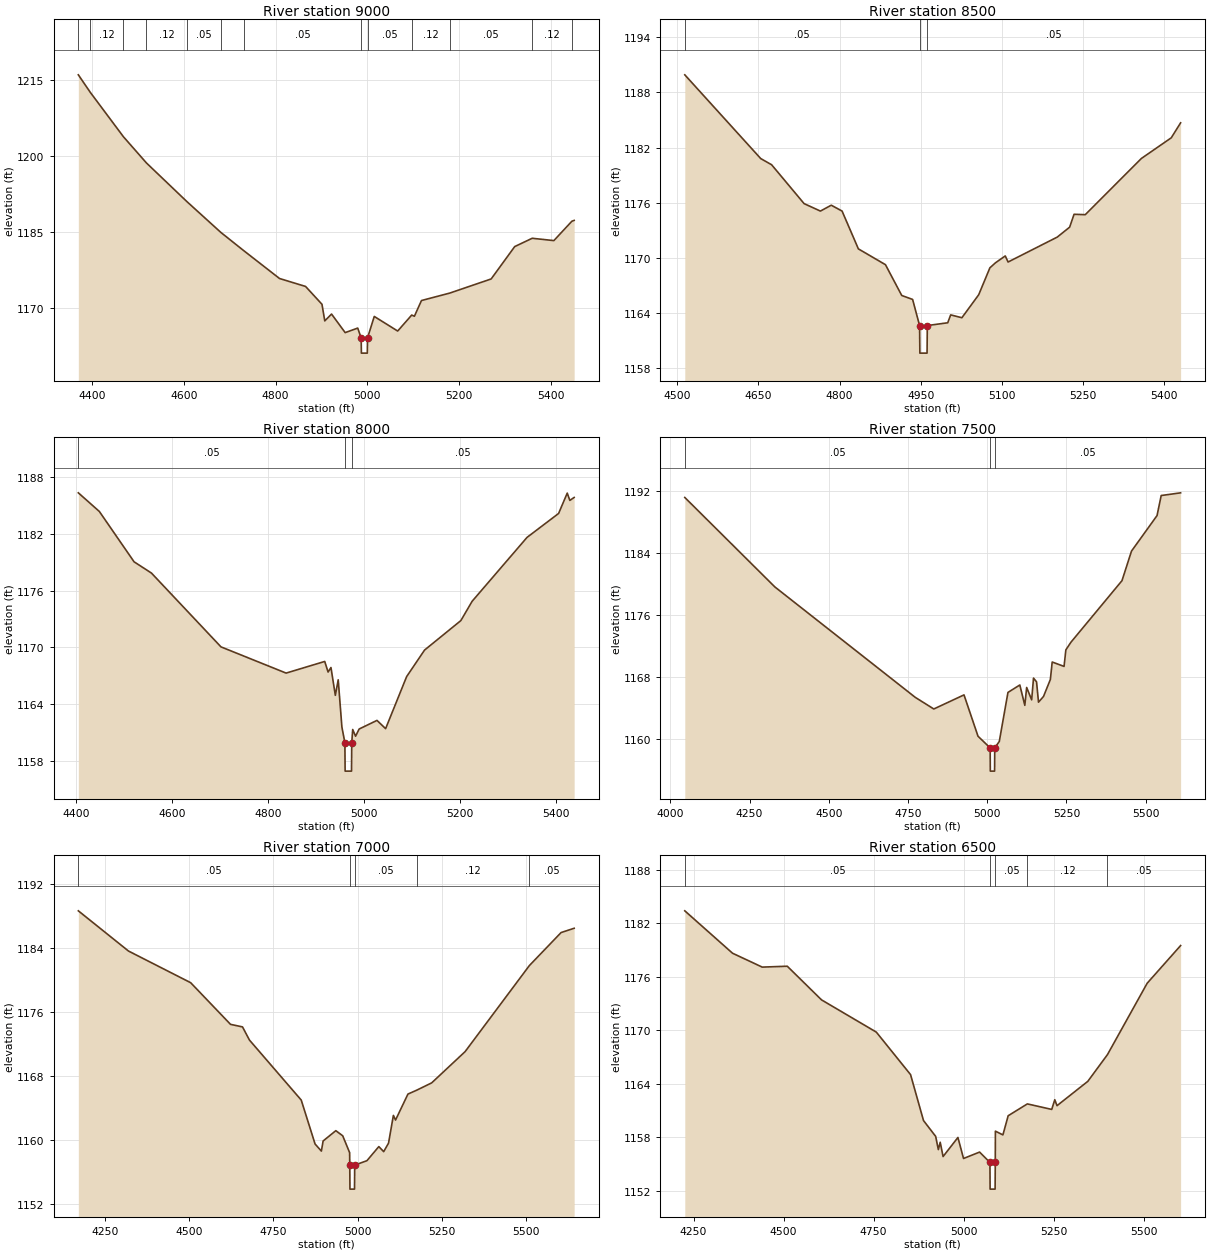
Type RM Length L Ch R = 1,9000,500,500,500
BEGIN DESCRIPTION:
VASTERLING CREEK 18.0
END DESCRIPTION:
XS GIS Cut Line= 3
      2747755.70     10218453.14      2748116.61     10218970.25
      2748355.70     10219353.13
#Sta/Elev= 30
  4369.4 1216.10  4395.6 1212.63  4467.9 1203.87  4518.1 1198.70  4606.3 1191.08
  4680.5 1184.99  4729.9 1181.43  4808.4 1175.90  4865.3 1174.33  4901.1 1170.81
  4907.2 1167.53  4922.0 1168.88  4951.7 1165.22  4979.1 1166.11  4986.6 1164.17
  4987.1 1161.17  5000.0 1161.17  5000.5 1164.17  5015.2 1168.41  5066.3 1165.53
  5096.9 1168.68  5102.8 1168.45  5118.2 1171.55  5179.9 1173.02  5270.3 1175.81
  5321.7 1182.20  5359.9 1183.84  5407.1 1183.38  5446.4 1187.20  5451.4 1187.37
#Mann=13,-1,0
  4369.4    0.05       0  4395.6    0.12       0  4467.9    0.05       0
  4518.1    0.12       0  4606.3    0.05       0  4680.5    0.12       0
  4729.9    0.05       0  4986.6    0.03       0  5000.5    0.05       0
  5096.9    0.12       0  5179.9    0.05       0  5359.9    0.12       0
  5446.4    0.05       0
Bank Sta=4986.6,5000.5
Exp/Cntr=0.3,0.1

Type RM Length L Ch R = 1,8500,500,500,500
BEGIN DESCRIPTION:
VASTERLING CREEK 17.0
END DESCRIPTION:
XS GIS Cut Line= 3
      2747305.68     10219303.11      2747790.42     10219339.36
      2748205.72     10219453.12
#Sta/Elev= 30
  4513.9 1189.92  4654.3 1180.81  4674.4 1180.14  4734.5 1175.91  4764.6 1175.10
  4784.7 1175.74  4804.7 1175.10  4834.8 1170.99  4884.9 1169.27  4915.0 1165.92
  4935.1 1165.49  4948.0 1162.65  4948.5 1159.65  4961.8 1159.65  4962.3 1162.65
  5000.0 1162.95  5005.5 1163.81  5026.2 1163.50  5057.3 1166.00  5078.0 1168.93
  5088.4 1169.48  5106.4 1170.22  5111.6 1169.56  5202.5 1172.27  5225.4 1173.35
  5233.6 1174.75  5254.3 1174.71  5358.0 1180.82  5413.3 1183.07  5430.6 1184.70
#Mann=3,-1,0
  4513.9    0.05       0  4948.0    0.03       0  4962.3    0.05       0
Bank Sta=4948,4962.3
Exp/Cntr=0.3,0.1

Type RM Length L Ch R = 1,8000,500,500,500
BEGIN DESCRIPTION:
VASTERLING CREEK 16.0
END DESCRIPTION:
XS GIS Cut Line= 3
      2747305.65     10219503.09      2747804.01     10219828.33
      2748205.66     10219653.12
#Sta/Elev= 30
  4404.9 1186.34  4448.7 1184.37  4521.1 1179.05  4557.3 1177.86  4702.2 1170.06
  4837.9 1167.29  4918.4 1168.52  4925.4 1167.40  4931.4 1167.88  4940.5 1164.94
  4946.5 1166.58  4954.2 1161.58  4960.4 1159.93  4960.9 1156.93  4974.2 1156.93
  4974.7 1159.93  4976.7 1161.33  4982.7 1160.62  4990.1 1161.38  5027.3 1162.29
  5045.3 1161.42  5089.1 1166.92  5126.4 1169.72  5202.1 1172.84  5225.6 1174.88
  5340.0 1181.63  5405.8 1184.16  5423.8 1186.31  5429.2 1185.54  5438.2 1185.85
#Mann=3,-1,0
  4404.9    0.05       0  4960.4    0.03       0  4974.7    0.05       0
Bank Sta=4960.4,4974.7
Exp/Cntr=0.3,0.1

Type RM Length L Ch R = 1,7500,500,500,500
BEGIN DESCRIPTION:
VASTERLING CREEK 15.0
END DESCRIPTION:
XS GIS Cut Line= 3
      2747251.82     10220738.81      2748070.56     10220248.74
      2748600.25     10219945.61
#Sta/Elev= 30
  4045.8 1191.22  4330.0 1179.66  4773.1 1165.39  4831.5 1163.89  4926.8 1165.71
  4971.0 1160.37  5009.3 1158.86  5009.8 1155.86  5023.3 1155.86  5023.8 1158.86
  5038.1 1159.69  5065.5 1166.03  5102.9 1166.99  5118.7 1164.36  5124.5 1166.67
  5140.3 1165.07  5146.1 1167.88  5155.7 1167.40  5161.9 1164.77  5177.7 1165.51
  5199.3 1167.70  5205.1 1169.96  5242.5 1169.39  5248.2 1171.53  5264.1 1172.51
  5425.3 1180.47  5455.3 1184.29  5535.9 1188.88  5549.0 1191.47  5610.3 1191.82
#Mann=3,-1,0
  4045.8    0.05       0  5009.3    0.05       0  5023.8    0.05       0
Bank Sta=5009.3,5023.8
Exp/Cntr=0.3,0.1

Type RM Length L Ch R = 1,7000,500,500,500
BEGIN DESCRIPTION:
VASTERLING CREEK 14.0
END DESCRIPTION:
XS GIS Cut Line= 3
      2747400.55     10220887.53      2748209.13     10220705.11
      2748709.35     10220302.53
#Sta/Elev= 30
  4171.1 1188.62  4319.9 1183.59  4504.4 1179.63  4622.6 1174.42  4658.2 1174.10
  4678.7 1172.46  4832.4 1164.95  4873.5 1159.45  4892.2 1158.57  4897.3 1159.83
  4935.0 1161.12  4955.5 1160.48  4976.0 1158.37  4976.4 1156.81  4976.9 1153.81
  4990.5 1153.81  4991.0 1156.81  5027.4 1157.37  5062.6 1159.13  5077.0 1158.50
  5091.4 1159.56  5105.8 1163.03  5112.2 1162.45  5149.0 1165.70  5174.7 1166.18
  5219.4 1167.10  5318.6 1171.01  5509.2 1181.77  5603.3 1185.90  5642.1 1186.44
#Mann=5,-1,0
  4171.1    0.05       0  4976.4    0.03       0  4991.0    0.05       0
  5174.7    0.12       0  5509.2    0.05       0
Bank Sta=4976.4,4991
Exp/Cntr=0.3,0.1

Type RM Length L Ch R = 1,6500,500,500,500
BEGIN DESCRIPTION:
VASTERLING CREEK 13.0
END DESCRIPTION:
XS GIS Cut Line= 3
      2747519.55     10221006.53      2748270.78     10221194.55
      2748755.70     10221553.12
#Sta/Elev= 30
  4225.6 1183.41  4358.2 1178.65  4440.7 1177.09  4510.3 1177.19  4605.5 1173.41
  4757.7 1169.79  4852.8 1165.02  4888.8 1159.86  4922.6 1158.08  4930.0 1156.60
  4935.2 1157.42  4943.2 1155.82  4984.4 1157.96  5000.0 1155.60  5044.6 1156.32
  5073.3 1155.16  5073.8 1152.16  5087.7 1152.16  5088.2 1155.16  5088.5 1158.67
  5109.4 1158.25  5124.0 1160.40  5177.3 1161.73  5245.0 1161.11  5253.5 1162.20
  5259.7 1161.53  5345.2 1164.26  5399.8 1167.26  5510.2 1175.28  5603.1 1179.51
#Mann=5,-1,0
  4225.6    0.05       0  5073.3    0.03       0  5088.2    0.05       0
  5177.3    0.12       0  5399.8    0.05       0
Bank Sta=5073.3,5088.2
Exp/Cntr=0.3,0.1

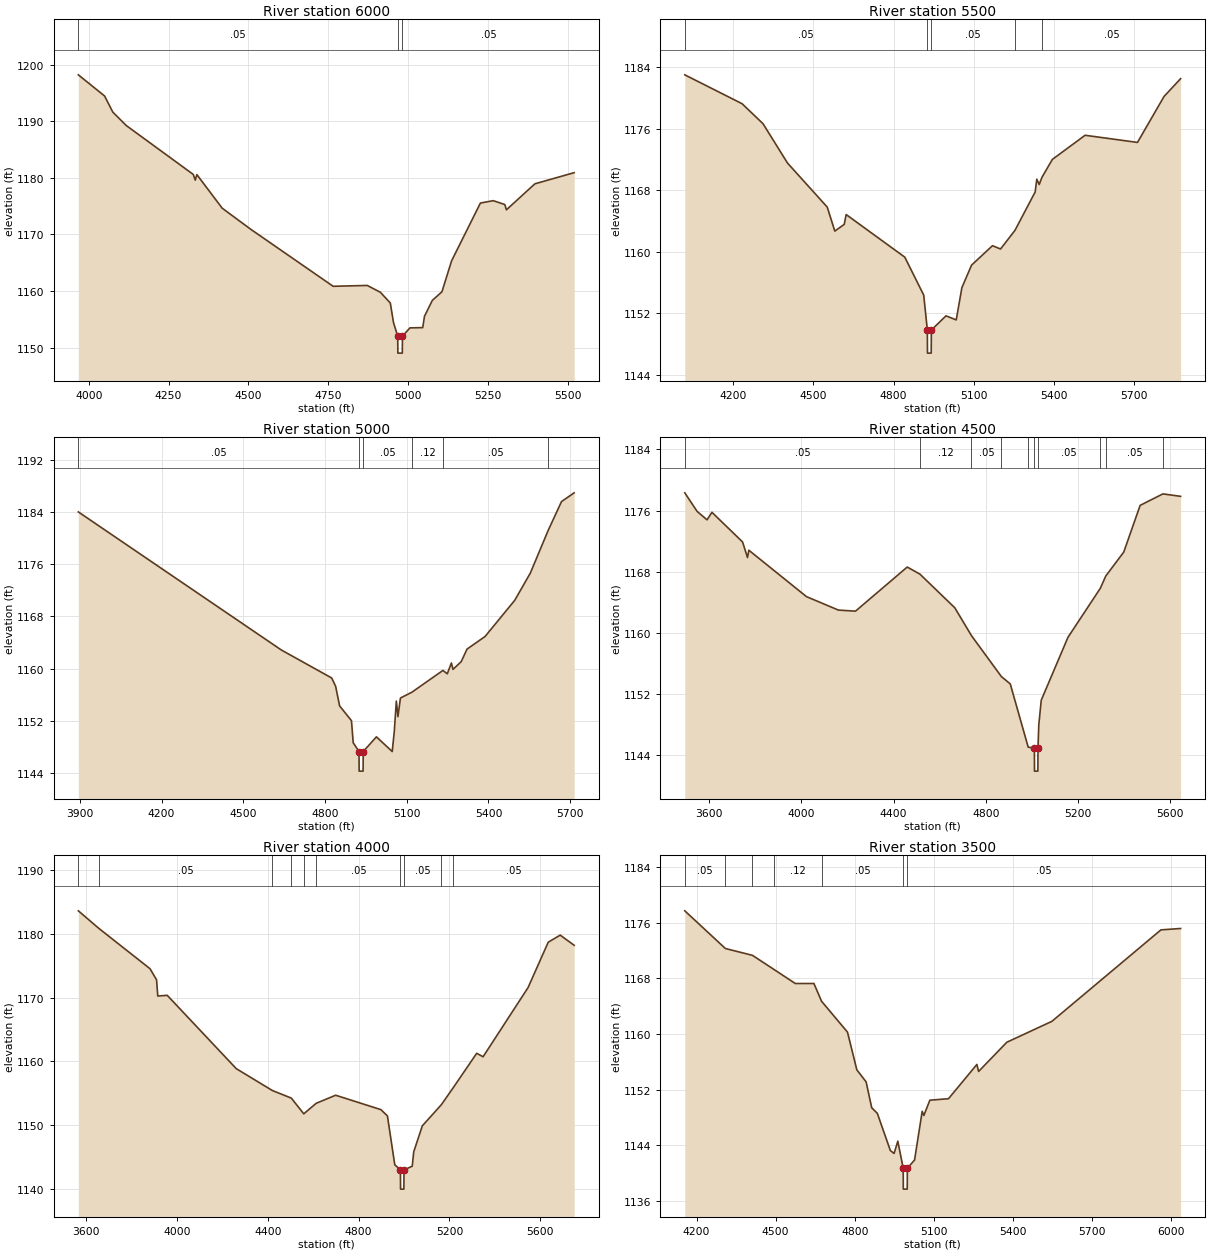
Type RM Length L Ch R = 1,6000,500,500,500
BEGIN DESCRIPTION:
VASTERLING CREEK 12.0
END DESCRIPTION:
XS GIS Cut Line= 3
      2747305.70     10221453.12      2748310.14     10221692.21
      2748828.30     10221651.00
#Sta/Elev= 30
  3967.5 1198.21  4049.7 1194.47  4075.4 1191.63  4117.6 1189.25  4327.3 1180.61
  4333.5 1179.60  4338.6 1180.58  4417.8 1174.65  4507.2 1170.92  4765.3 1160.84
  4872.1 1160.99  4913.2 1159.78  4944.2 1157.89  4954.3 1154.41  4967.4 1152.03
  4967.9 1149.03  4981.8 1149.03  4982.3 1152.03  5005.6 1153.49  5045.7 1153.54
  5051.2 1155.54  5075.8 1158.35  5105.9 1159.87  5136.0 1165.33  5226.3 1175.55
  5266.4 1175.97  5302.7 1175.29  5307.7 1174.35  5396.8 1178.95  5519.8 1180.92
#Mann=3,-1,0
  3967.5    0.05       0  4967.4    0.03       0  4982.3    0.05       0
Bank Sta=4967.4,4982.3
Exp/Cntr=0.3,0.1

Type RM Length L Ch R = 1,5500,500,500,500
BEGIN DESCRIPTION:
VASTERLING CREEK 11.0
END DESCRIPTION:
XS GIS Cut Line= 3
      2747519.51     10222870.57      2748185.50     10222149.74
      2748917.56     10221670.82
#Sta/Elev= 30
  4018.6 1183.00  4233.2 1179.24  4311.5 1176.64  4403.3 1171.52  4551.9 1165.80
  4580.2 1162.68  4615.4 1163.55  4622.8 1164.83  4842.2 1159.29  4913.1 1154.35
  4926.6 1149.81  4927.1 1146.81  4941.1 1146.81  4941.6 1149.81  4996.5 1151.66
  5034.8 1151.13  5055.9 1155.32  5092.1 1158.25  5170.4 1160.78  5200.6 1160.35
  5254.6 1162.77  5330.3 1167.77  5336.3 1169.43  5345.4 1168.74  5356.1 1169.70
  5394.6 1172.00  5517.2 1175.14  5713.3 1174.21  5812.8 1180.19  5874.8 1182.50
#Mann=5,-1,0
  4018.6    0.05       0  4926.6    0.05       0  4941.6    0.05       0
  5254.6    0.12       0  5356.1    0.05       0
Bank Sta=4926.6,4941.6
Exp/Cntr=0.3,0.1

Type RM Length L Ch R = 1,5000,500,500,500
BEGIN DESCRIPTION:
VASTERLING CREEK 10.0
END DESCRIPTION:
XS GIS Cut Line= 3
      2747737.63     10222989.56      2748616.03     10222318.65
      2749006.81     10221720.37
#Sta/Elev= 30
  3894.7 1184.00  4639.7 1162.86  4824.7 1158.57  4839.2 1157.29  4853.7 1154.30
  4897.3 1152.03  4903.6 1148.66  4924.9 1147.31  4925.4 1144.31  4939.9 1144.31
  4940.4 1147.31  4988.8 1149.56  5046.8 1147.31  5054.4 1150.38  5061.9 1155.03
  5067.8 1152.66  5077.0 1155.50  5118.9 1156.39  5233.0 1159.73  5248.9 1159.21
  5264.0 1160.87  5269.9 1159.89  5300.2 1161.08  5321.3 1162.99  5387.7 1164.93
  5496.3 1170.45  5553.6 1174.62  5619.4 1181.18  5668.2 1185.58  5714.6 1186.92
#Mann=6,-1,0
  3894.7    0.05       0  4924.9    0.03       0  4940.4    0.05       0
  5118.9    0.12       0  5233.0    0.05       0  5619.4    0.12       0
Bank Sta=4924.9,4940.4
Exp/Cntr=0.3,0.1

Type RM Length L Ch R = 1,4500,500,500,500
BEGIN DESCRIPTION:
VASTERLING CREEK 9.0
END DESCRIPTION:
XS GIS Cut Line= 3
      2747767.43     10223286.98      2749063.48     10222521.75
      2749264.58     10221908.79
#Sta/Elev= 30
  3494.9 1178.32  3548.4 1175.89  3591.3 1174.79  3612.7 1175.77  3745.5 1171.89
  3766.9 1169.85  3772.7 1170.81  4022.5 1164.74  4161.0 1162.98  4235.2 1162.84
  4459.5 1168.61  4514.7 1167.68  4665.8 1163.28  4738.0 1159.64  4867.8 1154.28
  4906.3 1153.32  4984.1 1145.05  5010.9 1144.91  5011.4 1141.91  5026.0 1141.91
  5026.5 1144.91  5030.1 1147.98  5040.7 1151.19  5156.6 1159.42  5296.9 1165.83
  5320.4 1167.43  5398.5 1170.57  5469.6 1176.68  5568.2 1178.18  5645.1 1177.86
#Mann=10,-1,0
  3494.9    0.05       0  4514.7    0.12       0  4738.0    0.05       0
  4867.8    0.12       0  4984.1    0.05       0  5010.9    0.05       0
  5026.5    0.05       0  5296.9    0.12       0  5320.4    0.05       0
  5568.2    0.12       0
Bank Sta=5010.9,5026.5
Exp/Cntr=0.3,0.1

Type RM Length L Ch R = 1,4000,500,500,500
BEGIN DESCRIPTION:
VASTERLING CREEK 8.0
END DESCRIPTION:
XS GIS Cut Line= 3
      2747965.67     10223505.14      2749283.20     10222937.03
      2749958.60     10222612.79
#Sta/Elev= 30
  3565.2 1183.56  3656.0 1180.80  3880.8 1174.51  3909.8 1172.76  3915.2 1170.23
  3956.8 1170.34  4260.8 1158.87  4419.7 1155.45  4503.4 1154.26  4558.2 1151.80
  4613.0 1153.45  4698.7 1154.71  4897.7 1152.46  4926.7 1151.48  4959.1 1143.83
  4984.0 1143.02  4984.5 1140.02  4999.2 1140.02  4999.7 1143.02  5036.0 1143.61
  5042.6 1145.86  5080.4 1149.92  5164.3 1153.23  5216.8 1155.90  5319.9 1161.27
  5348.1 1160.73  5546.3 1171.56  5635.0 1178.65  5687.8 1179.76  5749.2 1178.17
#Mann=10,-1,0
  3565.2    0.12       0  3656.0    0.05       0  4419.7    0.12       0
  4503.4    0.05       0  4558.2    0.12       0  4613.0    0.05       0
  4984.0    0.03       0  4999.7    0.05       0  5164.3    0.12       0
  5216.8    0.05       0
Bank Sta=4984,4999.7
Exp/Cntr=0.3,0.1

Type RM Length L Ch R = 1,3500,500,500,500
BEGIN DESCRIPTION:
VASTERLING CREEK 7.0
END DESCRIPTION:
XS GIS Cut Line= 3
      2748560.63     10224010.78      2749156.87     10223412.58
      2749978.47     10222781.32
#Sta/Elev= 30
  4155.4 1177.71  4309.4 1172.29  4412.0 1171.31  4493.6 1169.28  4574.5 1167.26
  4645.2 1167.26  4674.1 1164.71  4772.5 1160.27  4807.9 1154.85  4843.2 1153.11
  4864.4 1149.39  4885.7 1148.59  4935.1 1143.24  4949.3 1142.82  4963.4 1144.59
  4983.8 1140.69  4984.3 1137.69  4999.1 1137.69  4999.6 1140.69  5026.9 1141.88
  5055.9 1148.88  5062.2 1148.28  5084.9 1150.48  5155.6 1150.69  5263.3 1155.62
  5269.8 1154.61  5376.8 1158.81  5548.0 1161.82  5961.3 1174.97  6036.1 1175.17
#Mann=7,-1,0
  4155.4    0.05       0  4309.4    0.12       0  4412.0    0.05       0
  4493.6    0.12       0  4674.1    0.05       0  4983.8    0.03       0
  4999.6    0.05       0
Bank Sta=4983.8,4999.6
Exp/Cntr=0.3,0.1

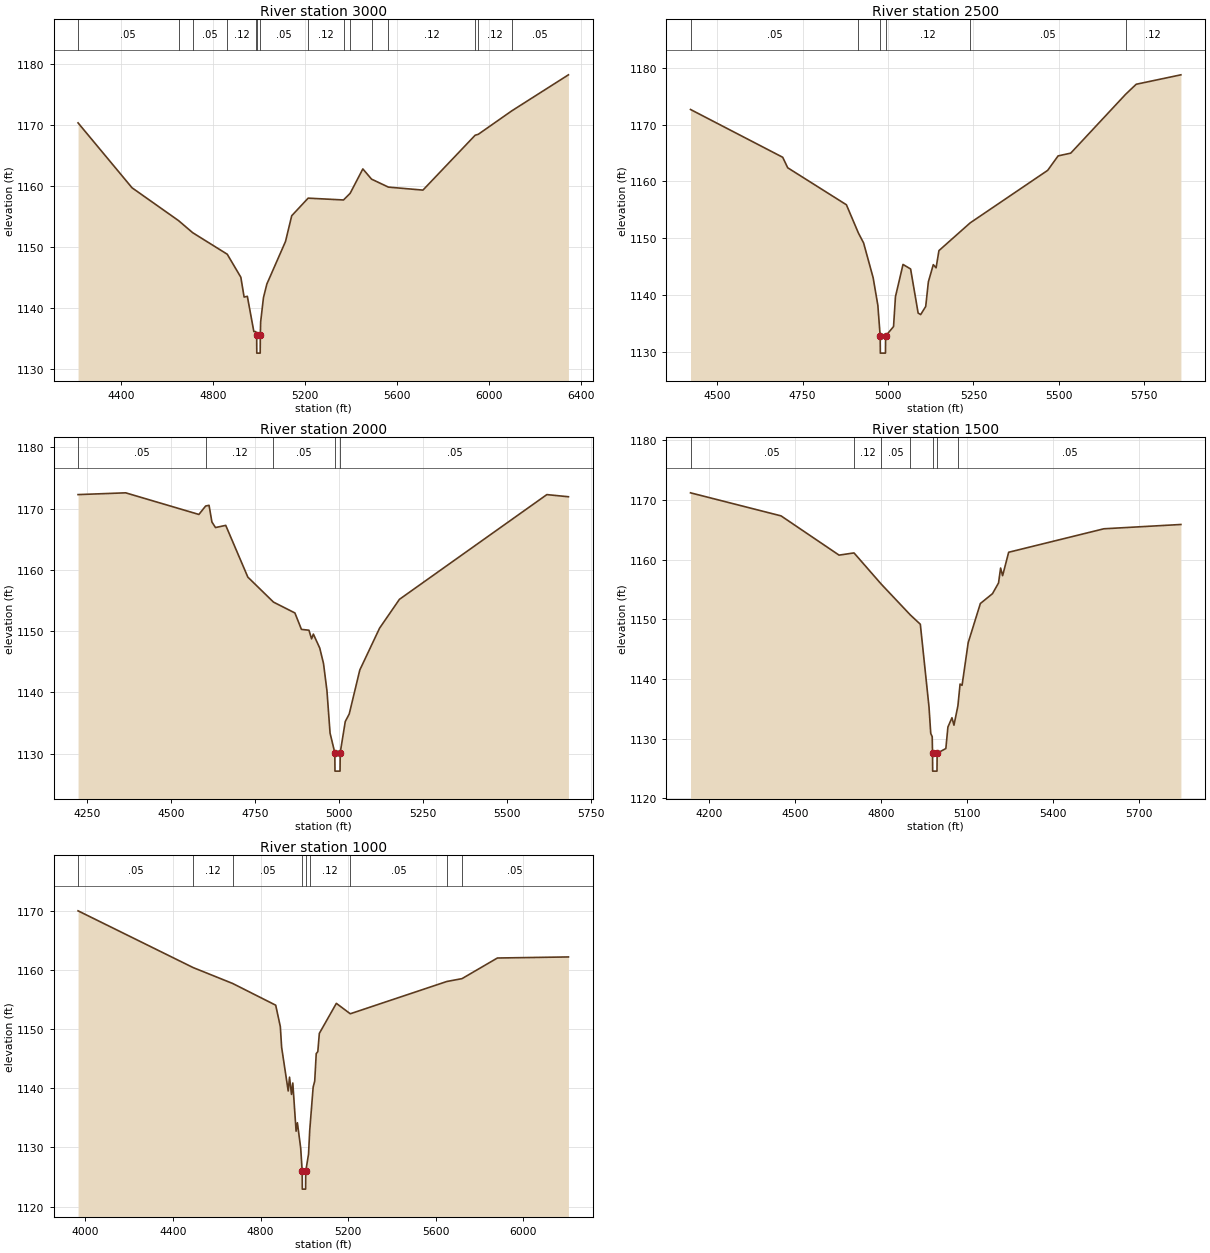
Type RM Length L Ch R = 1,3000,500,500,500
BEGIN DESCRIPTION:
VASTERLING CREEK 6.0
END DESCRIPTION:
XS GIS Cut Line= 3
      2748930.61     10224320.34      2749489.34     10223765.38
      2750611.85     10223020.08
#Sta/Elev= 30
  4212.5 1170.37  4447.5 1159.71  4650.0 1154.32  4711.4 1152.34  4862.0 1148.80
  4921.2 1145.02  4935.4 1141.77  4949.5 1141.89  4977.8 1136.10  4986.2 1136.09
  4990.1 1135.56  4990.6 1132.56  5005.5 1132.56  5006.0 1135.56  5007.4 1137.68
  5019.6 1141.66  5034.4 1143.90  5115.6 1150.89  5142.7 1155.12  5214.2 1158.01
  5368.2 1157.71  5397.0 1158.80  5452.4 1162.81  5490.2 1161.13  5563.7 1159.82
  5714.0 1159.33  5941.3 1168.34  5955.2 1168.50  6100.6 1172.34  6347.4 1178.26
#Mann=15,-1,0
  4212.5    0.05       0  4650.0    0.12       0  4711.4    0.05       0
  4862.0    0.12       0  4986.2    0.05       0  4990.1    0.05       0
  5006.0    0.05       0  5214.2    0.12       0  5368.2    0.05       0
  5397.0    0.12       0  5490.2    0.05       0  5563.7    0.12       0
  5941.3    0.05       0  5955.2    0.12       0  6100.6    0.05       0
Bank Sta=4990.1,5006
Exp/Cntr=0.3,0.1

Type RM Length L Ch R = 1,2500,500,500,500
BEGIN DESCRIPTION:
VASTERLING CREEK 5.0
END DESCRIPTION:
XS GIS Cut Line= 3
      2749522.35     10224556.16      2749860.84     10224087.77
      2750621.84     10223694.09
#Sta/Elev= 30
  4422.1 1172.65  4691.8 1164.24  4706.5 1162.39  4878.2 1155.88  4913.2 1150.92
  4928.5 1149.16  4956.4 1143.04  4970.2 1138.18  4977.0 1132.77  4977.5 1129.77
  4992.4 1129.77  4992.9 1132.77  5016.1 1134.45  5021.7 1139.70  5043.8 1145.38
  5066.0 1144.58  5088.1 1136.81  5095.5 1136.56  5110.2 1137.98  5118.0 1142.32
  5132.4 1145.34  5140.6 1144.79  5148.9 1147.81  5240.2 1152.69  5467.1 1161.94
  5497.5 1164.48  5534.6 1164.97  5695.2 1175.33  5726.0 1177.09  5856.8 1178.75
#Mann=6,-1,0
  4422.1    0.05       0  4913.2    0.12       0  4977.0    0.07       0
  4992.9    0.12       0  5240.2    0.05       0  5695.2    0.12       0
Bank Sta=4977,4992.9
Exp/Cntr=0.3,0.1

Type RM Length L Ch R = 1,2000,500,500,500
BEGIN DESCRIPTION:
VASTERLING CREEK 4.0
END DESCRIPTION:
XS GIS Cut Line= 3
      2749413.28     10224694.95      2750139.47     10224420.00
      2750731.36     10224080.58
#Sta/Elev= 30
  4223.5 1172.27  4365.1 1172.56  4583.0 1169.03  4603.1 1170.41  4613.2 1170.52
  4621.7 1167.80  4632.4 1166.89  4662.8 1167.25  4728.6 1158.80  4804.9 1154.72
  4868.6 1152.95  4888.0 1150.27  4910.4 1150.13  4918.2 1148.72  4923.5 1149.50
  4942.5 1147.22  4953.7 1144.69  4963.9 1140.28  4973.2 1133.33  4987.3 1130.13
  4987.8 1127.13  5002.9 1127.13  5003.4 1130.13  5018.4 1135.23  5030.2 1136.46
  5061.6 1143.63  5120.5 1150.47  5179.5 1155.17  5618.1 1172.27  5682.3 1171.92
#Mann=5,-1,0
  4223.5    0.05       0  4603.1    0.12       0  4804.9    0.05       0
  4987.3    0.05       0  5003.4    0.05       0
Bank Sta=4987.3,5003.4
Exp/Cntr=0.3,0.1

Type RM Length L Ch R = 1,1500,500,500,500
BEGIN DESCRIPTION:
VASTERLING CREEK 3.0
END DESCRIPTION:
XS GIS Cut Line= 3
      2749373.67     10224764.36      2750228.31     10224902.25
      2750840.91     10224318.34
#Sta/Elev= 30
  4134.3 1171.17  4450.4 1167.31  4652.9 1160.74  4705.1 1161.11  4800.3 1155.88
  4902.1 1150.71  4936.6 1149.17  4966.9 1135.33  4973.0 1130.88  4978.1 1130.35
  4979.2 1127.58  4979.7 1124.58  4994.8 1124.58  4995.3 1127.58  5025.7 1128.36
  5032.9 1131.96  5047.1 1133.52  5054.0 1132.27  5067.8 1135.51  5075.4 1139.16
  5082.3 1138.94  5103.7 1146.08  5146.2 1152.64  5188.6 1154.29  5209.7 1156.09
  5216.9 1158.58  5223.9 1157.30  5245.0 1161.22  5577.4 1165.15  5846.3 1165.87
#Mann=7,-1,0
  4134.3    0.05       0  4705.1    0.12       0  4800.3    0.05       0
  4902.1    0.12       0  4979.2    0.07       0  4995.3    0.12       0
  5067.8    0.05       0
Bank Sta=4979.2,4995.3
Exp/Cntr=0.3,0.1

Type RM Length L Ch R = 1,1000,0,0,0
BEGIN DESCRIPTION:
VASTERLING CREEK 2.0
END DESCRIPTION:
XS GIS Cut Line= 3
      2749334.01     10224823.86      2750193.64     10225397.93
      2751028.67     10224527.22
#Sta/Elev= 30
  3966.3 1170.01  4492.1 1160.41  4672.7 1157.72  4869.2 1154.05  4890.3 1150.42
  4896.3 1146.91  4926.3 1139.54  4932.3 1141.88  4941.3 1138.96  4947.3 1140.89
  4962.3 1132.74  4968.3 1134.17  4983.4 1129.86  4990.2 1125.94  4990.7 1122.94
  5005.8 1122.94  5006.3 1125.94  5019.1 1128.85  5024.5 1132.83  5040.2 1140.18
  5047.4 1141.22  5054.3 1145.86  5061.6 1146.20  5068.5 1149.28  5146.2 1154.36
  5209.8 1152.60  5651.0 1158.06  5720.2 1158.54  5881.8 1162.03  6206.4 1162.21
#Mann=9,-1,0
  3966.3    0.05       0  4492.1    0.12       0  4672.7    0.05       0
  4990.2    0.05       0  5006.3    0.05       0  5024.5    0.12       0
  5209.8    0.05       0  5651.0    0.05       0  5720.2    0.05       0
Bank Sta=4990.2,5006.3
Exp/Cntr=0.3,0.1

Chan Stop Cuts=-1