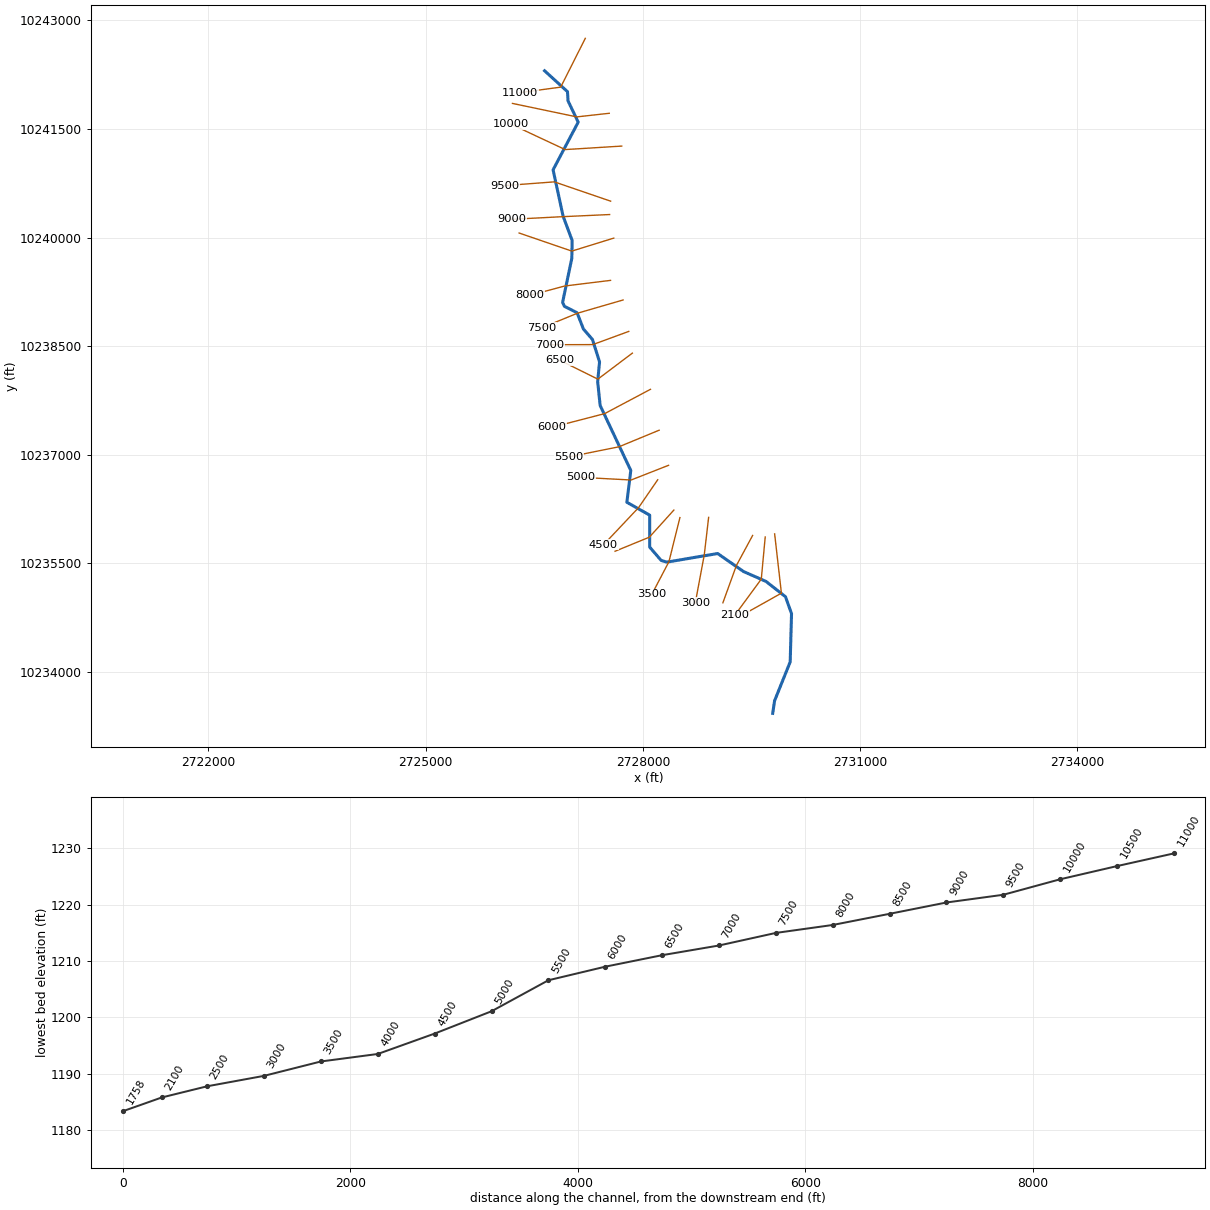
--- WEIDE CREEK.prj (project) ---

Proj Title=WEIDE CREEK Base Level Engineering
Current Plan=p01
Default Exp/Contr=0.3,0.1
English Units
Geom File=g01
Flow File=f01
Plan File=p01
BEGIN DESCRIPTION:
WEIDE CREEK
END DESCRIPTION:

--- WEIDE CREEK.p01 (plan) ---

Plan Title=Multiple Run
Short Identifier=Multiple
Geom File=g01
Flow File=f01
Subcritical Flow
K Sum by GR= 0
Std Step Tol= 0.01
Critical Tol= 0.01
Num of Std Step Trials= 20
Max Error Tol= 0.3
Flow Tol Ratio= 0.001
Split Flow NTrial= 30
Split Flow Tol= 0.02
Split Flow Ratio= 0.02
Log Output Level= 0
Friction Slope Method= 1
Unsteady Friction Slope Method= 2
Unsteady Bridges Friction Slope Method= 1
Parabolic Critical Depth
Global Vel Dist=  1 , 1 , 1
Global Log Level= 0
CheckData=True
Encroach Param= -1, 0, 0, 0
BEGIN DESCRIPTION:
Multiple Run
END DESCRIPTION:

--- WEIDE CREEK.f01 (steady flow) ---

Flow Title=Multiple
Number of Profiles=7
Profile Names=10-year,25-year,50-year,1pct_min,100-year,1pct_plu,500-year
River Rch & RM= WEIDE CREEK,Reach-1,11000
     188     411     682     371    1122    3387    3218
River Rch & RM= WEIDE CREEK,Reach-1,6000
     213     472     786     430    1298    3919    3753
River Rch & RM= WEIDE CREEK,Reach-1,4500
     236     526     881     483    1458    4404    4243
River Rch & RM= WEIDE CREEK,Reach-1,3500
     257     575     966     531    1603    4841    4688
Boundary for River Rch & Prof#=WEIDE CREEK,Reach-1,1
Up Type=0
Dn Type=3
Dn Slope=0.005
Boundary for River Rch & Prof#=WEIDE CREEK,Reach-1,2
Up Type=0
Dn Type=3
Dn Slope=0.005
Boundary for River Rch & Prof#=WEIDE CREEK,Reach-1,3
Up Type=0
Dn Type=3
Dn Slope=0.005
Boundary for River Rch & Prof#=WEIDE CREEK,Reach-1,4
Up Type=0
Dn Type=3
Dn Slope=0.005
Boundary for River Rch & Prof#=WEIDE CREEK,Reach-1,5
Up Type=0
Dn Type=3
Dn Slope=0.005
Boundary for River Rch & Prof#=WEIDE CREEK,Reach-1,6
Up Type=0
Dn Type=3
Dn Slope=0.005
Boundary for River Rch & Prof#=WEIDE CREEK,Reach-1,7
Up Type=0
Dn Type=3
Dn Slope=0.005

--- WEIDE CREEK.g01 (geometry) ---

Geom Title=Existing Conditions

River Reach=WEIDE CREEK,Reach-1
Reach XY= 30
      2726643.25     10242305.00      2726960.00     10242016.00
      2726967.25     10241889.00      2727107.75     10241595.00
      2726761.00     10240936.00      2726898.50     10240298.00
      2727024.00     10239960.00      2727019.75     10239714.00
      2726892.25     10239104.00      2726917.50     10239050.00
      2727092.25     10238961.00      2727180.00     10238736.00
      2727304.75     10238592.00      2727402.50     10238282.00
      2727376.50     10238008.00      2727411.00     10237679.00
      2727833.75     10236782.00      2727779.75     10236342.00
      2728095.25     10236164.00      2728094.75     10235723.00
      2728252.75     10235539.00      2728332.25     10235515.00
      2729033.25     10235634.00      2729390.75     10235385.00
      2729701.50     10235248.00      2729969.75     10235037.00
      2730053.50     10234803.00      2730035.00     10234136.00
      2729819.25     10233599.00      2729793.50     10233425.00

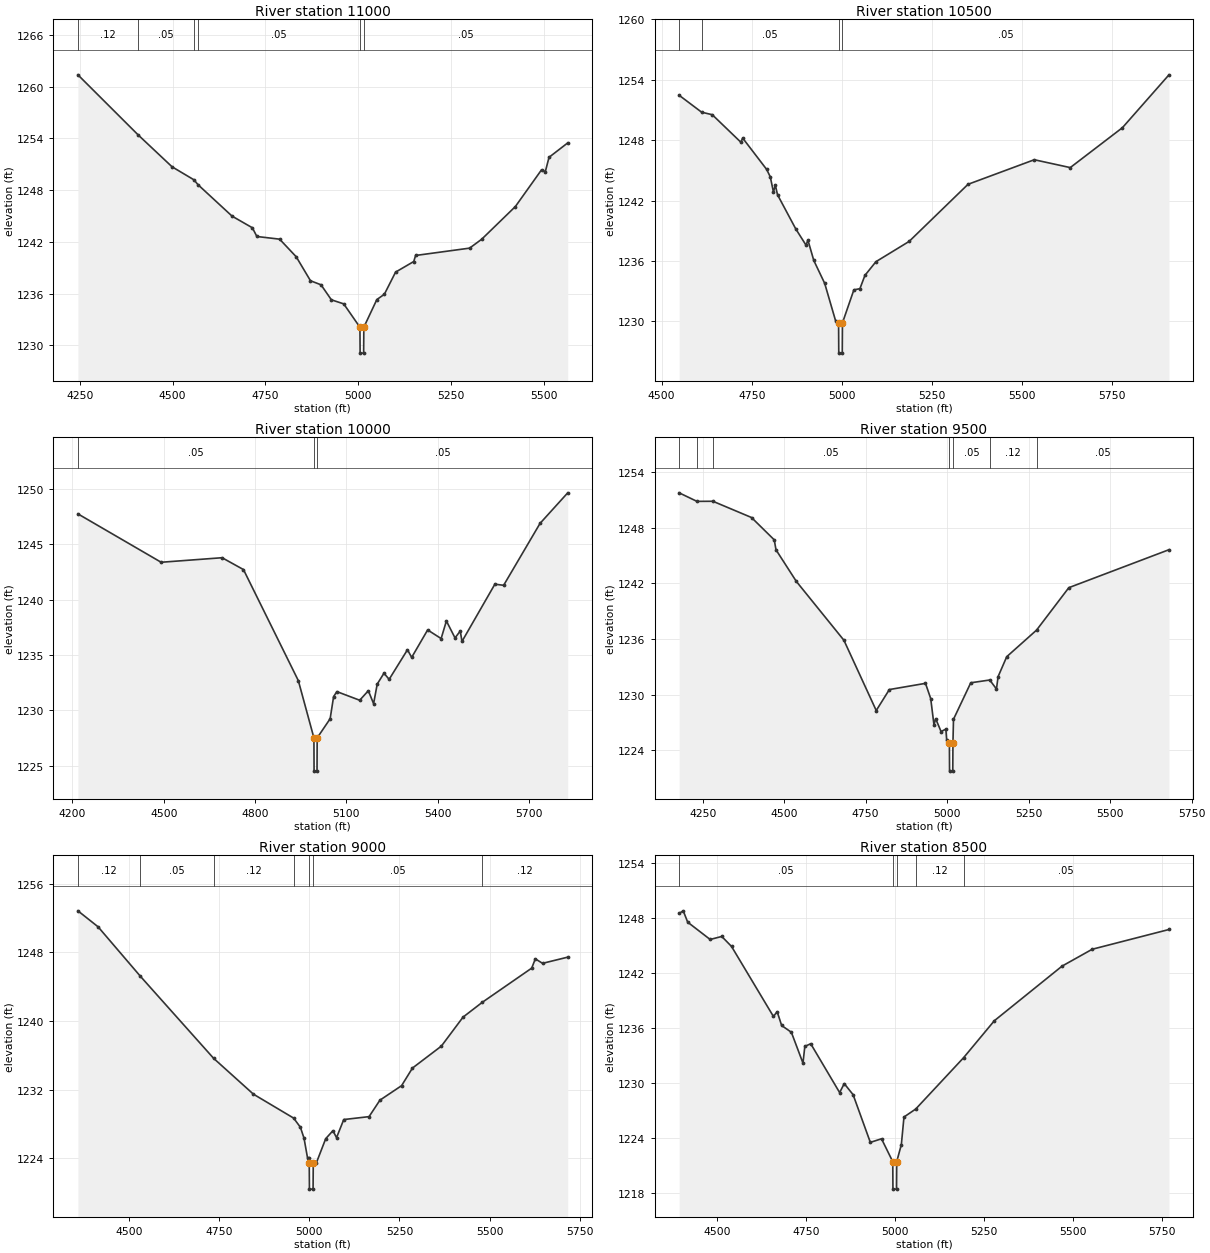
Type RM Length L Ch R = 1,11000,500,500,500
BEGIN DESCRIPTION:
WEIDE CREEK 22.0
END DESCRIPTION:
XS GIS Cut Line= 3
      2727205.69     10242753.12      2726865.95     10242078.65
      2726305.72     10242003.12
#Sta/Elev= 30
  4244.8 1261.36  4407.8 1254.37  4498.6 1250.70  4557.6 1249.19  4568.7 1248.62
  4660.4 1244.98  4715.1 1243.63  4727.3 1242.62  4788.6 1242.31  4833.3 1240.27
  4871.8 1237.49  4900.2 1237.02  4928.1 1235.28  4961.4 1234.81  5005.1 1232.10
  5005.6 1229.10  5015.1 1229.10  5015.6 1232.10  5050.7 1235.31  5070.9 1235.92
  5101.2 1238.49  5150.2 1239.72  5155.2 1240.42  5300.7 1241.27  5333.3 1242.30
  5424.1 1246.09  5494.7 1250.35  5504.8 1250.13  5514.9 1251.80  5565.3 1253.47
#Mann=6,-1,0
  4244.8    0.12       0  4407.8    0.05       0  4557.6    0.12       0
  4568.7    0.05       0  5005.1    0.03       0  5015.6    0.05       0
Bank Sta=5005.1,5015.6
Exp/Cntr=0.3,0.1

Type RM Length L Ch R = 1,10500,500,500,500
BEGIN DESCRIPTION:
WEIDE CREEK 21.0
END DESCRIPTION:
XS GIS Cut Line= 3
      2727537.02     10241717.48      2727088.29     10241667.54
      2726199.99     10241853.75
#Sta/Elev= 30
  4548.5 1252.45  4610.9 1250.77  4640.4 1250.52  4719.7 1247.79  4724.8 1248.20
  4791.3 1245.09  4801.4 1244.35  4810.2 1242.84  4815.3 1243.54  4821.5 1242.57
  4871.8 1239.20  4900.7 1237.56  4905.7 1238.08  4922.1 1236.05  4952.3 1233.78
  4982.5 1230.07  4990.9 1229.85  4991.4 1226.85  5001.1 1226.85  5001.6 1229.85
  5033.3 1233.13  5050.1 1233.25  5064.0 1234.57  5094.6 1235.93  5186.6 1237.94
  5350.0 1243.61  5533.9 1246.05  5633.7 1245.27  5778.4 1249.23  5907.6 1254.48
#Mann=4,-1,0
  4548.5    0.12       0  4610.9    0.05       0  4990.9    0.03       0
  5001.6    0.05       0
Bank Sta=4990.9,5001.6
Exp/Cntr=0.3,0.1

Type RM Length L Ch R = 1,10000,500,500,500
BEGIN DESCRIPTION:
WEIDE CREEK 20.0
END DESCRIPTION:
XS GIS Cut Line= 3
      2727708.61     10241264.22      2726927.92     10241215.70
      2726178.94     10241567.07
#Sta/Elev= 30
  4217.8 1247.74  4491.3 1243.37  4691.6 1243.78  4761.8 1242.71  4942.1 1232.68
  4993.3 1227.51  4993.8 1224.51  5003.5 1224.51  5004.0 1227.51  5046.6 1229.24
  5058.0 1231.24  5068.7 1231.69  5143.7 1230.91  5172.1 1231.77  5189.4 1230.60
  5201.3 1232.37  5223.4 1233.35  5240.5 1232.80  5300.7 1235.47  5314.5 1234.78
  5367.0 1237.26  5411.3 1236.48  5428.6 1238.07  5456.9 1236.54  5474.2 1237.16
  5479.8 1236.22  5587.9 1241.39  5616.7 1241.29  5736.3 1246.88  5827.3 1249.64
#Mann=3,-1,0
  4217.8    0.05       0  4993.3    0.03       0  5004.0    0.05       0
Bank Sta=4993.3,5004
Exp/Cntr=0.3,0.1

Type RM Length L Ch R = 1,9500,500,500,500
BEGIN DESCRIPTION:
WEIDE CREEK 19.0
END DESCRIPTION:
XS GIS Cut Line= 3
      2727555.65     10240503.12      2726777.88     10240769.73
      2726099.40     10240718.66
#Sta/Elev= 30
  4177.8 1251.75  4232.4 1250.83  4281.4 1250.84  4399.8 1249.09  4469.6 1246.68
  4474.9 1245.61  4537.4 1242.20  4683.3 1235.86  4782.4 1228.29  4822.6 1230.55
  4933.5 1231.22  4949.5 1229.58  4959.5 1226.75  4964.7 1227.41  4981.2 1226.03
  4996.0 1226.28  4998.5 1225.08  5006.8 1224.76  5007.3 1221.76  5017.2 1221.76
  5017.7 1224.76  5019.4 1227.35  5072.4 1231.28  5130.6 1231.58  5151.2 1230.61
  5156.2 1231.94  5182.7 1234.09  5274.3 1236.96  5373.2 1241.53  5680.4 1245.62
#Mann=7,-1,0
  4177.8    0.05       0  4232.4    0.12       0  4281.4    0.05       0
  5006.8    0.03       0  5017.7    0.05       0  5130.6    0.12       0
  5274.3    0.05       0
Bank Sta=5006.8,5017.7
Exp/Cntr=0.3,0.1

Type RM Length L Ch R = 1,9000,500,500,500
BEGIN DESCRIPTION:
WEIDE CREEK 18.0
END DESCRIPTION:
XS GIS Cut Line= 3
      2727541.43     10240318.11      2726901.29     10240289.07
      2726186.05     10240252.10
#Sta/Elev= 30
  4359.2 1252.83  4415.0 1250.97  4532.5 1245.19  4735.1 1235.64  4845.4 1231.46
  4956.8 1228.67  4975.6 1227.60  4985.6 1226.33  4995.3 1224.04  5000.0 1224.04
  5000.1 1223.39  5000.6 1220.39  5010.7 1220.39  5011.2 1223.39  5019.6 1223.43
  5045.7 1226.27  5065.7 1227.20  5075.7 1226.39  5095.7 1228.50  5165.8 1228.84
  5195.9 1230.76  5255.9 1232.45  5286.0 1234.50  5366.1 1237.06  5426.2 1240.44
  5479.3 1242.16  5616.4 1246.15  5626.4 1247.23  5646.5 1246.71  5716.2 1247.43
#Mann=7,-1,0
  4359.2    0.12       0  4532.5    0.05       0  4735.1    0.12       0
  4956.8    0.05       0  5000.1    0.03       0  5011.2    0.05       0
  5479.3    0.12       0
Bank Sta=5000.1,5011.2
Exp/Cntr=0.3,0.1

Type RM Length L Ch R = 1,8500,500,500,500
BEGIN DESCRIPTION:
WEIDE CREEK 17.0
END DESCRIPTION:
XS GIS Cut Line= 3
      2727598.61     10239992.46      2727019.71     10239812.94
      2726291.71     10240062.86
#Sta/Elev= 30
  4393.9 1248.51  4405.4 1248.79  4417.9 1247.55  4481.0 1245.66  4513.6 1245.99
  4541.0 1244.90  4658.7 1237.25  4669.2 1237.77  4681.8 1236.26  4709.1 1235.52
  4741.7 1232.15  4746.9 1233.97  4763.4 1234.27  4844.7 1228.93  4857.6 1229.91
  4882.5 1228.70  4930.9 1223.49  4962.3 1223.88  4993.9 1221.38  4994.4 1218.38
  5004.5 1218.38  5005.0 1221.38  5018.0 1223.24  5025.4 1226.26  5058.3 1227.13
  5192.6 1232.73  5279.2 1236.78  5469.5 1242.75  5554.0 1244.59  5769.7 1246.75
#Mann=5,-1,0
  4393.9    0.05       0  4993.9    0.05       0  5005.0    0.05       0
  5058.3    0.12       0  5192.6    0.05       0
Bank Sta=4993.9,5005
Exp/Cntr=0.3,0.1

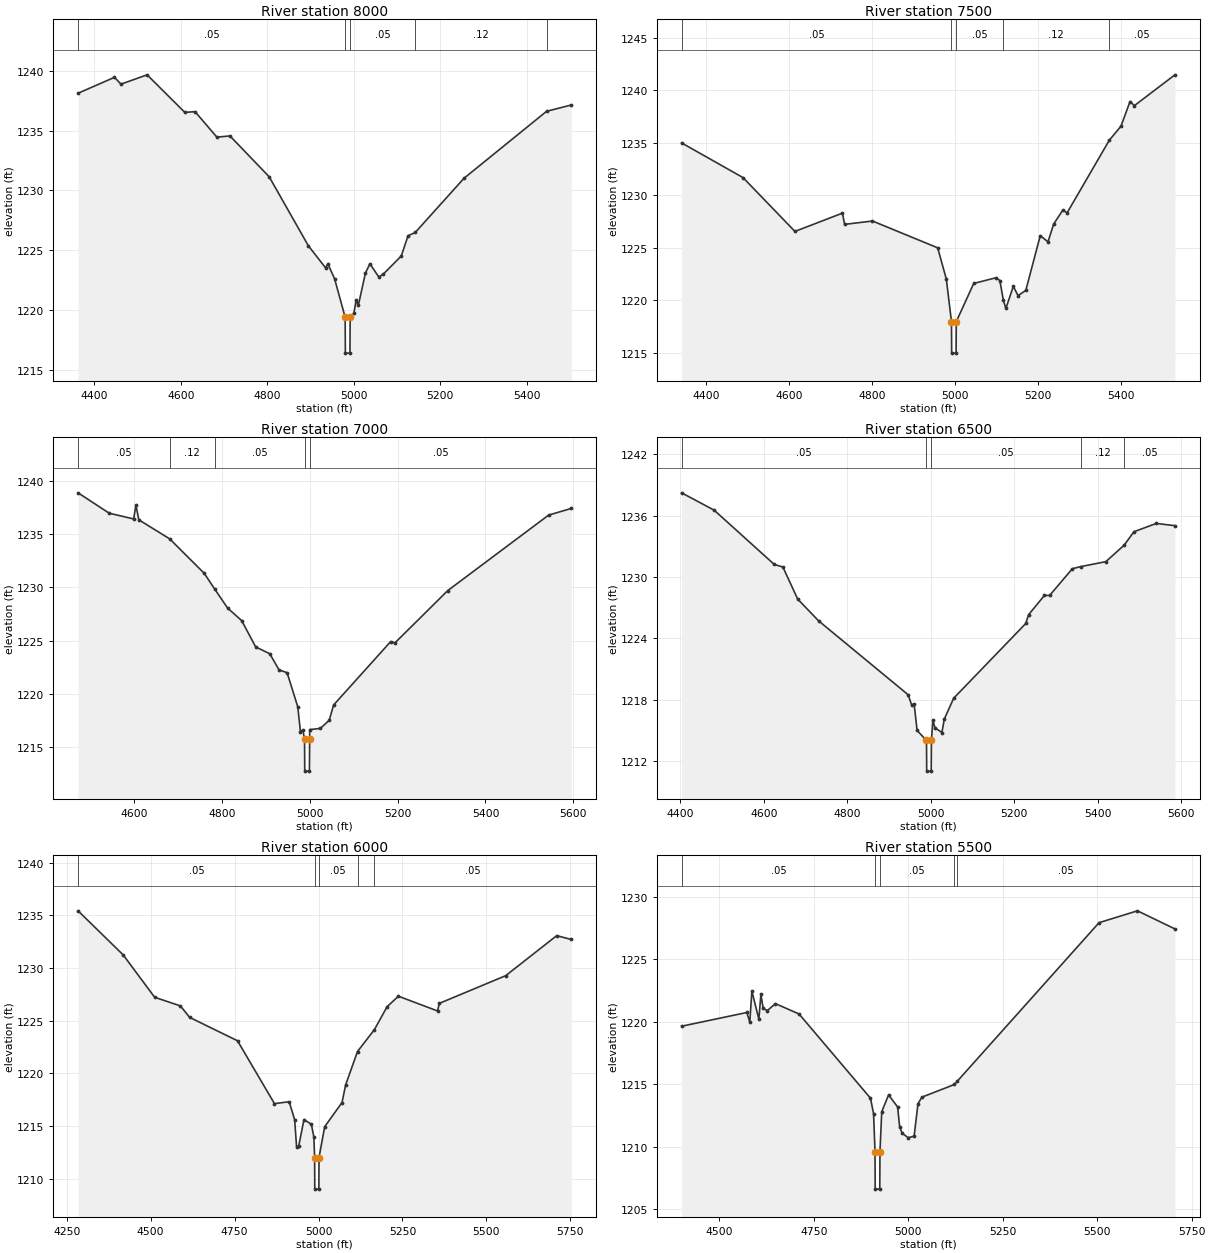
Type RM Length L Ch R = 1,8000,500,500,500
BEGIN DESCRIPTION:
WEIDE CREEK 16.0
END DESCRIPTION:
XS GIS Cut Line= 3
      2727554.04     10239408.37      2726921.59     10239330.71
      2726436.07     10239200.05
#Sta/Elev= 30
  4362.8 1238.13  4446.9 1239.46  4461.9 1238.89  4522.3 1239.67  4609.5 1236.53
  4633.2 1236.59  4683.5 1234.46  4713.8 1234.56  4804.4 1231.15  4895.1 1225.37
  4934.8 1223.53  4939.9 1223.87  4955.6 1222.62  4980.0 1219.40  4980.5 1216.40
  4991.1 1216.40  4991.6 1219.40  5000.0 1219.72  5005.5 1220.81  5010.6 1220.41
  5026.8 1223.09  5037.2 1223.87  5057.9 1222.76  5068.3 1223.01  5109.7 1224.52
  5125.3 1226.21  5142.0 1226.49  5254.7 1231.02  5445.5 1236.62  5502.8 1237.15
#Mann=5,-1,0
  4362.8    0.05       0  4980.0    0.03       0  4991.6    0.05       0
  5142.0    0.12       0  5445.5    0.05       0
Bank Sta=4980,4991.6
Exp/Cntr=0.3,0.1

Type RM Length L Ch R = 1,7500,500,500,500
BEGIN DESCRIPTION:
WEIDE CREEK 15.0
END DESCRIPTION:
XS GIS Cut Line= 3
      2727727.70     10239137.54      2727095.72     10238953.96
      2726605.69     10238753.11
#Sta/Elev= 30
  4341.9 1234.99  4489.8 1231.69  4614.7 1226.57  4729.1 1228.31  4734.3 1227.24
  4801.4 1227.56  4958.4 1225.01  4979.2 1222.04  4991.6 1217.99  4992.1 1214.99
  5002.7 1214.99  5003.2 1217.99  5045.2 1221.62  5098.6 1222.16  5108.1 1221.90
  5116.6 1220.01  5122.6 1219.24  5140.5 1221.34  5152.0 1220.46  5170.6 1220.96
  5205.4 1226.17  5224.0 1225.58  5237.8 1227.28  5259.4 1228.58  5270.2 1228.35
  5371.5 1235.24  5399.9 1236.59  5421.5 1238.93  5432.1 1238.54  5529.6 1241.47
#Mann=5,-1,0
  4341.9    0.05       0  4991.6    0.03       0  5003.2    0.05       0
  5116.6    0.12       0  5371.5    0.05       0
Bank Sta=4991.6,5003.2
Exp/Cntr=0.3,0.1

Type RM Length L Ch R = 1,7000,500,500,500
BEGIN DESCRIPTION:
WEIDE CREEK 14.0
END DESCRIPTION:
XS GIS Cut Line= 3
      2727805.71     10238703.12      2727309.58     10238521.00
      2726713.78     10238519.48
#Sta/Elev= 30
  4471.5 1238.85  4542.4 1236.94  4598.1 1236.40  4603.4 1237.69  4610.0 1236.32
  4680.4 1234.53  4759.1 1231.30  4783.2 1229.81  4812.4 1228.04  4844.4 1226.87
  4876.3 1224.40  4908.3 1223.77  4929.6 1222.25  4947.9 1221.99  4972.2 1218.79
  4978.4 1216.43  4983.8 1216.62  4987.6 1215.76  4988.1 1212.76  4998.8 1212.76
  4999.3 1215.76  4999.4 1216.65  5023.9 1216.77  5043.9 1217.53  5053.9 1218.96
  5183.9 1224.90  5193.9 1224.79  5313.9 1229.68  5543.9 1236.76  5595.8 1237.39
#Mann=5,-1,0
  4471.5    0.05       0  4680.4    0.12       0  4783.2    0.05       0
  4987.6    0.03       0  4999.3    0.05       0
Bank Sta=4987.6,4999.3
Exp/Cntr=0.3,0.1

Type RM Length L Ch R = 1,6500,500,500,500
BEGIN DESCRIPTION:
WEIDE CREEK 13.0
END DESCRIPTION:
XS GIS Cut Line= 3
      2727855.69     10238403.12      2727379.40     10238043.68
      2726855.73     10238303.09
#Sta/Elev= 30
  4403.3 1238.22  4481.4 1236.52  4625.0 1231.23  4645.8 1230.97  4681.2 1227.84
  4731.2 1225.72  4945.6 1218.50  4953.9 1217.52  4960.1 1217.58  4967.1 1215.01
  4989.6 1214.04  4990.1 1211.04  5000.9 1211.04  5001.4 1214.04  5004.9 1215.99
  5009.9 1215.27  5026.5 1214.81  5032.3 1216.13  5054.7 1218.16  5227.3 1225.46
  5234.1 1226.32  5272.0 1228.20  5284.5 1228.20  5338.9 1230.81  5358.6 1231.01
  5419.1 1231.50  5462.9 1233.11  5486.3 1234.42  5539.8 1235.23  5584.4 1235.01
#Mann=5,-1,0
  4403.3    0.05       0  4989.6    0.03       0  5001.4    0.05       0
  5358.6    0.12       0  5462.9    0.05       0
Bank Sta=4989.6,5001.4
Exp/Cntr=0.3,0.1

Type RM Length L Ch R = 1,6000,500,500,500
BEGIN DESCRIPTION:
WEIDE CREEK 12.0
END DESCRIPTION:
XS GIS Cut Line= 3
      2728105.68     10237903.11      2727473.45     10237567.24
      2726744.70     10237378.12
#Sta/Elev= 30
  4284.1 1235.43  4418.5 1231.24  4512.1 1227.22  4588.7 1226.40  4616.3 1225.31
  4758.8 1223.09  4868.8 1217.12  4912.7 1217.30  4929.0 1215.58  4934.7 1213.02
  4940.9 1213.07  4956.7 1215.60  4978.7 1215.16  4986.2 1213.95  4988.4 1212.00
  4988.9 1209.00  5001.0 1209.00  5001.5 1212.00  5018.4 1214.93  5070.0 1217.22
  5080.8 1218.90  5116.1 1222.07  5166.5 1224.15  5204.3 1226.33  5237.9 1227.32
  5354.5 1225.92  5359.6 1226.64  5557.3 1229.27  5709.2 1233.07  5752.9 1232.71
#Mann=5,-1,0
  4284.1    0.05       0  4988.4    0.03       0  5001.5    0.05       0
  5116.1    0.12       0  5166.5    0.05       0
Bank Sta=4988.4,5001.5
Exp/Cntr=0.3,0.1

Type RM Length L Ch R = 1,5500,500,500,500
BEGIN DESCRIPTION:
WEIDE CREEK 11.0
END DESCRIPTION:
XS GIS Cut Line= 3
      2728225.17     10237337.97      2727670.83     10237108.90
      2726979.06     10236969.40
#Sta/Elev= 30
  4400.2 1219.65  4572.8 1220.75  4580.6 1219.98  4586.1 1222.46  4604.6 1220.21
  4610.0 1222.20  4616.0 1221.09  4626.9 1220.90  4648.5 1221.46  4711.0 1220.63
  4900.0 1213.88  4908.2 1212.63  4912.0 1209.59  4912.5 1206.59  4924.6 1206.59
  4925.1 1209.59  4929.8 1212.80  4947.9 1214.14  4971.8 1213.18  4977.2 1211.60
  4983.9 1211.07  5000.0 1210.71  5015.5 1210.84  5025.7 1213.43  5035.9 1213.96
  5122.3 1214.98  5129.4 1215.23  5504.9 1227.95  5606.5 1228.90  5705.7 1227.45
#Mann=5,-1,0
  4400.2    0.05       0  4912.0    0.03       0  4925.1    0.05       0
  5122.3    0.12       0  5129.4    0.05       0
Bank Sta=4912,4925.1
Exp/Cntr=0.3,0.1

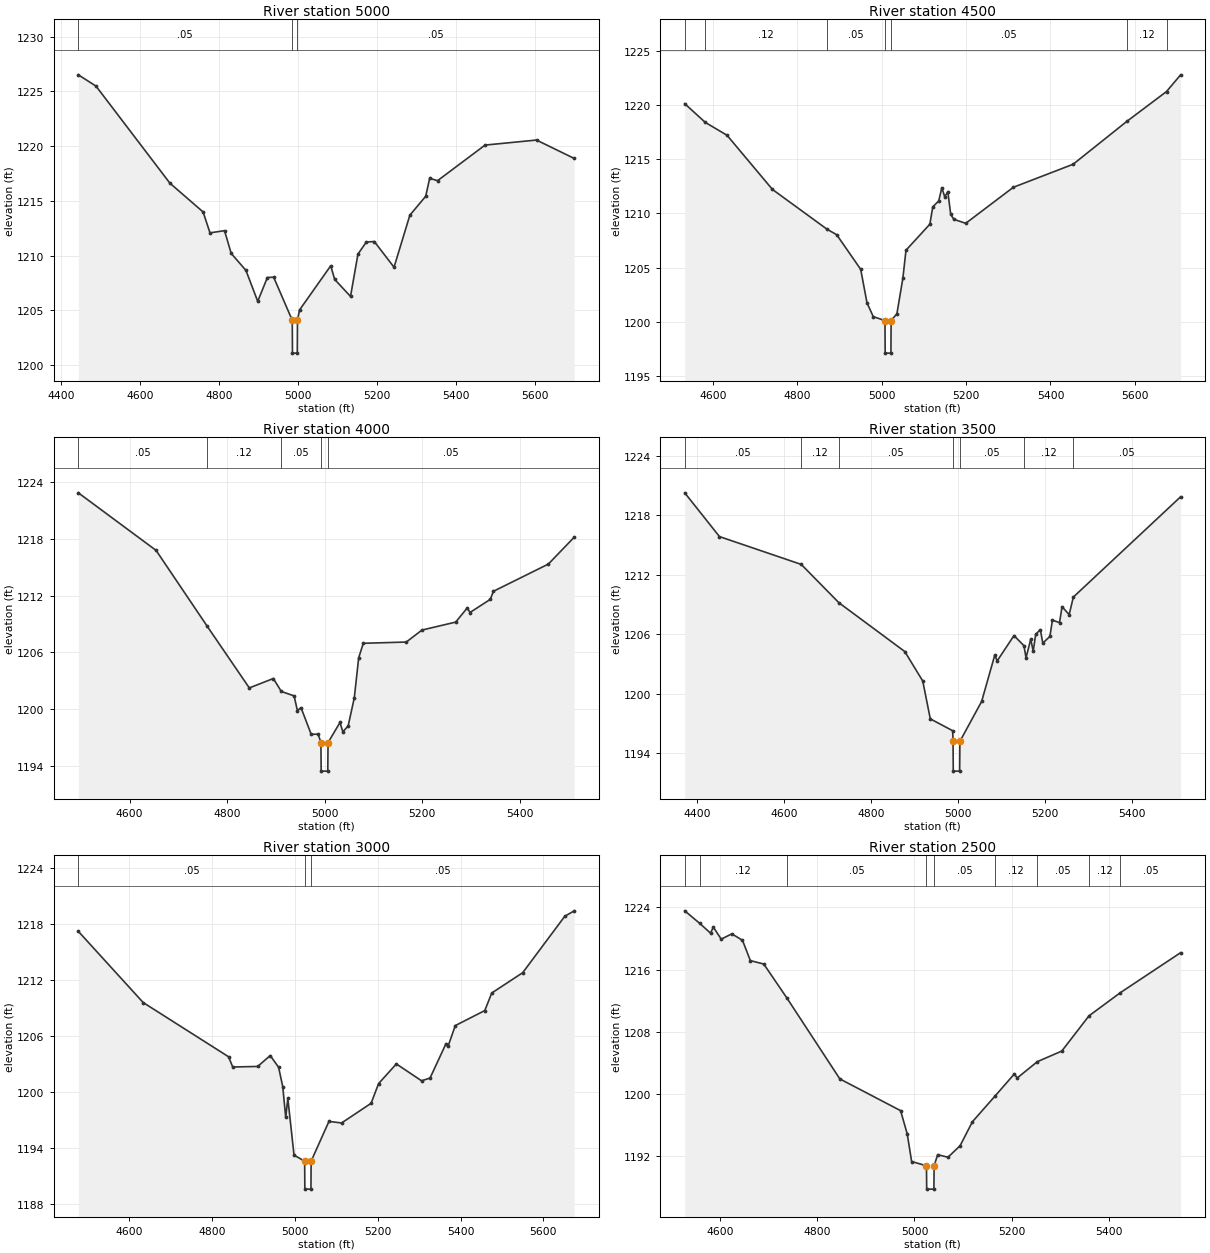
Type RM Length L Ch R = 1,5000,500,500,500
BEGIN DESCRIPTION:
WEIDE CREEK 10.0
END DESCRIPTION:
XS GIS Cut Line= 3
      2728355.66     10236853.10      2727838.46     10236649.86
      2727140.45     10236686.92
#Sta/Elev= 30
  4444.3 1226.52  4489.0 1225.49  4676.0 1216.62  4760.0 1213.99  4777.4 1212.08
  4814.2 1212.28  4831.1 1210.20  4868.4 1208.65  4898.2 1205.82  4922.6 1208.00
  4938.5 1208.03  4985.6 1204.09  4986.1 1201.09  4998.3 1201.09  4998.8 1204.09
  5003.9 1205.03  5082.9 1209.07  5092.9 1207.83  5133.0 1206.27  5151.8 1210.14
  5173.0 1211.24  5193.1 1211.29  5243.1 1208.94  5283.2 1213.70  5323.2 1215.42
  5333.2 1217.06  5353.3 1216.85  5473.4 1220.10  5603.6 1220.56  5699.0 1218.88
#Mann=3,-1,0
  4444.3    0.05       0  4985.6    0.03       0  4998.8    0.05       0
Bank Sta=4985.6,4998.8
Exp/Cntr=0.3,0.1

Type RM Length L Ch R = 1,4500,500,500,500
BEGIN DESCRIPTION:
WEIDE CREEK 9.0
END DESCRIPTION:
XS GIS Cut Line= 3
      2728205.70     10236653.13      2727941.69     10236268.53
      2727455.69     10235753.12
#Sta/Elev= 30
  4533.5 1220.11  4582.1 1218.39  4633.7 1217.20  4741.3 1212.21  4870.5 1208.55
  4893.5 1208.04  4950.4 1204.85  4965.3 1201.77  4980.2 1200.49  5007.9 1200.13
  5008.4 1197.13  5022.0 1197.13  5022.5 1200.13  5036.2 1200.76  5050.4 1204.05
  5057.7 1206.61  5114.3 1209.01  5121.2 1210.61  5135.3 1211.15  5142.6 1212.37
  5149.5 1211.53  5156.8 1212.01  5163.7 1209.92  5170.9 1209.46  5199.3 1209.09
  5312.1 1212.41  5453.7 1214.53  5580.9 1218.48  5675.0 1221.23  5708.4 1222.77
#Mann=7,-1,0
  4533.5    0.05       0  4582.1    0.12       0  4870.5    0.05       0
  5007.9    0.03       0  5022.5    0.05       0  5580.9    0.12       0
  5675.0    0.05       0
Bank Sta=5007.9,5022.5
Exp/Cntr=0.3,0.1

Type RM Length L Ch R = 1,4000,500,500,500
BEGIN DESCRIPTION:
WEIDE CREEK 8.0
END DESCRIPTION:
XS GIS Cut Line= 3
      2728429.09     10236234.77      2728090.42     10235859.90
      2727616.61     10235665.33
#Sta/Elev= 30
  4494.8 1222.81  4654.3 1216.75  4759.5 1208.74  4845.6 1202.27  4894.9 1203.26
  4911.2 1201.90  4937.5 1201.43  4944.2 1199.89  4951.7 1200.19  4972.6 1197.38
  4986.8 1197.41  4992.5 1196.51  4993.0 1193.51  5006.6 1193.51  5007.1 1196.51
  5031.6 1198.63  5037.5 1197.65  5048.4 1198.27  5061.0 1201.23  5070.0 1205.45
  5079.5 1206.97  5167.7 1207.10  5199.7 1208.36  5269.0 1209.20  5292.9 1210.70
  5298.3 1210.21  5340.2 1211.60  5346.3 1212.44  5459.2 1215.31  5512.2 1218.14
#Mann=5,-1,0
  4494.8    0.05       0  4759.5    0.12       0  4911.2    0.05       0
  4992.5    0.03       0  5007.1    0.05       0
Bank Sta=4992.5,5007.1
Exp/Cntr=0.3,0.1

Type RM Length L Ch R = 1,3500,500,500,500
BEGIN DESCRIPTION:
WEIDE CREEK 7.0
END DESCRIPTION:
XS GIS Cut Line= 3
      2728512.40     10236130.55      2728360.50     10235520.69
      2728123.52     10235068.08
#Sta/Elev= 30
  4371.5 1220.29  4451.3 1215.87  4639.2 1213.06  4725.7 1209.19  4877.1 1204.26
  4918.4 1201.28  4935.7 1197.46  4987.2 1196.26  4988.0 1195.18  4988.5 1192.18
  5003.2 1192.18  5003.7 1195.18  5053.7 1199.22  5083.9 1203.90  5089.5 1203.32
  5128.0 1205.87  5150.9 1204.85  5155.7 1203.63  5166.5 1205.50  5172.2 1204.30
  5177.9 1206.00  5188.6 1206.47  5194.2 1205.11  5210.6 1205.79  5216.3 1207.43
  5232.7 1207.18  5238.4 1208.79  5254.8 1207.99  5264.4 1209.76  5510.9 1219.89
#Mann=7,-1,0
  4371.5    0.05       0  4639.2    0.12       0  4725.7    0.05       0
  4988.0    0.03       0  5003.7    0.05       0  5150.9    0.12       0
  5264.4    0.05       0
Bank Sta=4988,5003.7
Exp/Cntr=0.3,0.1

Type RM Length L Ch R = 1,3000,500,500,500
BEGIN DESCRIPTION:
WEIDE CREEK 6.0
END DESCRIPTION:
XS GIS Cut Line= 3
      2728908.77     10236133.53      2728848.36     10235613.83
      2728724.32     10234950.83
#Sta/Elev= 30
  4476.8 1217.26  4633.4 1209.63  4839.6 1203.82  4849.7 1202.72  4910.1 1202.78
  4940.3 1203.95  4960.5 1202.69  4970.5 1200.62  4977.7 1197.32  4982.8 1199.35
  4997.8 1193.27  5023.4 1192.63  5023.9 1189.63  5038.6 1189.63  5039.1 1192.63
  5082.1 1196.89  5112.6 1196.72  5183.9 1198.83  5202.0 1200.94  5244.9 1203.05
  5305.9 1201.24  5326.3 1201.54  5364.9 1205.23  5370.0 1204.97  5387.3 1207.16
  5458.5 1208.77  5475.3 1210.65  5550.1 1212.83  5651.8 1218.88  5674.5 1219.46
#Mann=3,-1,0
  4476.8    0.05       0  5023.4    0.03       0  5039.1    0.05       0
Bank Sta=5023.4,5039.1
Exp/Cntr=0.3,0.1

Type RM Length L Ch R = 1,2500,400,400,400
BEGIN DESCRIPTION:
WEIDE CREEK 5.0
END DESCRIPTION:
XS GIS Cut Line= 3
      2729516.40     10235883.96      2729292.08     10235468.00
      2729105.68     10234953.10
#Sta/Elev= 30
  4527.4 1223.56  4557.8 1221.97  4580.5 1220.69  4586.2 1221.47  4602.4 1219.92
  4624.3 1220.60  4646.2 1219.77  4662.4 1217.16  4690.0 1216.72  4737.7 1212.34
  4846.5 1201.95  4971.5 1197.87  4985.2 1194.86  4994.2 1191.33  5024.7 1190.78
  5025.2 1187.78  5040.0 1187.78  5040.5 1190.78  5047.7 1192.21  5069.0 1191.88
  5093.9 1193.36  5119.2 1196.44  5165.0 1199.69  5205.8 1202.61  5211.2 1202.06
  5252.9 1204.17  5303.1 1205.53  5359.1 1210.06  5423.9 1213.05  5547.6 1218.18
#Mann=9,-1,0
  4527.4    0.05       0  4557.8    0.12       0  4737.7    0.05       0
  5024.7    0.03       0  5040.5    0.05       0  5165.0    0.12       0
  5252.9    0.05       0  5359.1    0.12       0  5423.9    0.05       0
Bank Sta=5024.7,5040.5
Exp/Cntr=0.3,0.1

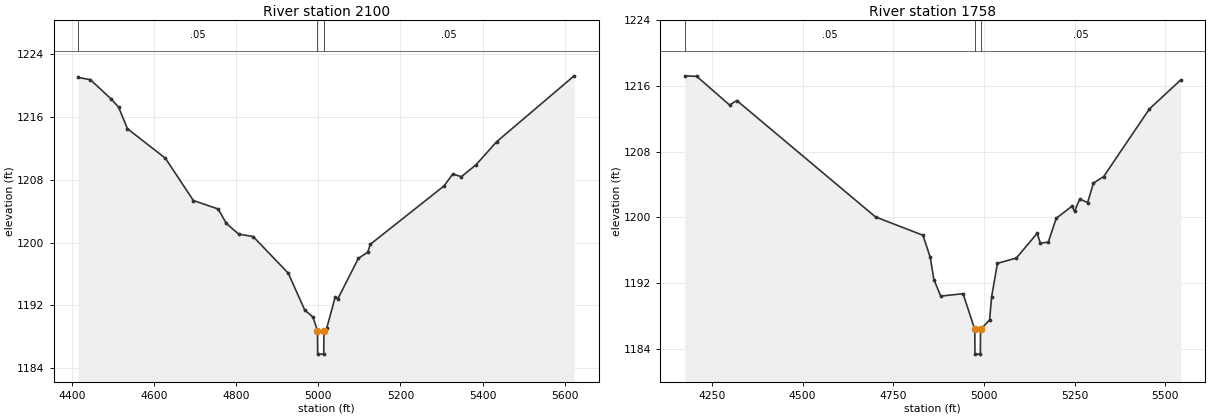
Type RM Length L Ch R = 1,2100,342,342,342
BEGIN DESCRIPTION:
WEIDE CREEK 4.0
END DESCRIPTION:
XS GIS Cut Line= 3
      2729690.03     10235862.30      2729636.00     10235280.00
      2729267.18     10234777.66
#Sta/Elev= 30
  4415.2 1221.03  4444.5 1220.75  4494.7 1218.31  4513.1 1217.27  4534.9 1214.50
  4627.4 1210.74  4695.6 1205.35  4755.8 1204.28  4775.9 1202.43  4806.1 1201.07
  4841.1 1200.77  4926.6 1196.10  4966.7 1191.42  4986.8 1190.50  4997.8 1188.79
  4998.3 1185.79  5013.1 1185.79  5013.6 1188.79  5020.3 1189.08  5041.2 1193.10
  5047.4 1192.83  5097.5 1197.99  5120.2 1198.77  5126.8 1199.79  5306.3 1207.22
  5327.5 1208.74  5348.3 1208.39  5383.8 1209.89  5434.0 1212.83  5623.2 1221.24
#Mann=3,-1,0
  4415.2    0.05       0  4997.8    0.03       0  5013.6    0.05       0
Bank Sta=4997.8,5013.6
Exp/Cntr=0.3,0.1

Type RM Length L Ch R = 1,1758,0,0,0
BEGIN DESCRIPTION:
WEIDE CREEK 3.0
END DESCRIPTION:
XS GIS Cut Line= 3
      2729820.23     10235905.68      2729913.75     10235086.00
      2729440.56     10234820.67
#Sta/Elev= 30
  4175.0 1217.23  4207.8 1217.17  4298.4 1213.68  4318.5 1214.22  4701.0 1200.05
  4831.8 1197.82  4851.9 1195.15  4862.0 1192.42  4880.9 1190.41  4942.5 1190.71
  4974.8 1186.35  4975.3 1183.35  4990.2 1183.35  4990.7 1186.35  5015.6 1187.50
  5021.3 1190.35  5037.2 1194.40  5089.5 1195.05  5146.8 1198.06  5155.9 1196.85
  5177.6 1196.99  5199.3 1199.88  5242.7 1201.36  5250.0 1200.75  5264.3 1202.23
  5286.0 1201.80  5302.0 1204.17  5330.3 1204.97  5456.4 1213.20  5542.5 1216.72
#Mann=3,-1,0
  4175.0    0.05       0  4974.8    0.05       0  4990.7    0.05       0
Bank Sta=4974.8,4990.7
Exp/Cntr=0.3,0.1

Chan Stop Cuts=-1