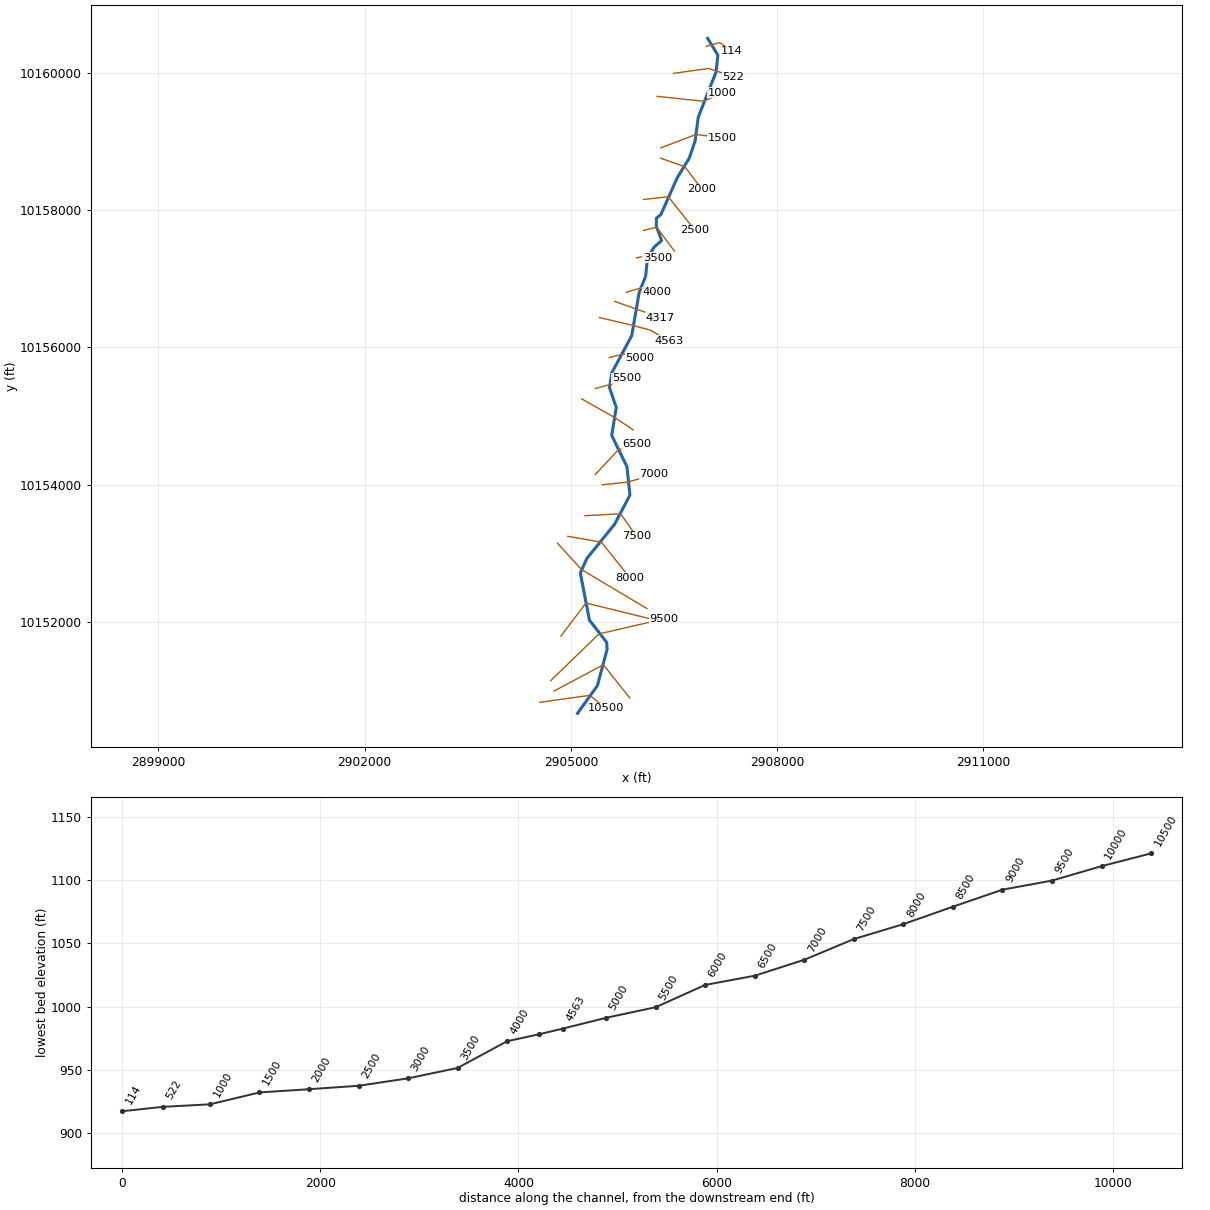
--- CEDAR BRANCH.prj (project) ---

Proj Title=CEDAR BRANCH Base Level Engineering
Current Plan=p01
Default Exp/Contr=0.3,0.1
English Units
Geom File=g01
Flow File=f01
Plan File=p01
Y Axis Title=Elevation
X Axis Title(PF)=Main Channel Distance
X Axis Title(XS)=Station
BEGIN DESCRIPTION:
CEDAR BRANCH
END DESCRIPTION:
DSS Export Rating Curves= 0
DSS Export Rating Curve Sorted= 0
DSS Export Volume Flow Curves= 0
DXF OffsetX= 0
DXF OffsetY= 0
DXF ScaleX= 1
DXF ScaleY= 10

--- CEDAR BRANCH.p01 (plan) ---

Plan Title=Multiple Run
Short Identifier=Multiple
Geom File=g01
Flow File=f01
Subcritical Flow
K Sum by GR= 0
Std Step Tol= 0.01
Critical Tol= 0.01
Num of Std Step Trials= 20
Max Error Tol= 0.3
Flow Tol Ratio= 0.001
Split Flow NTrial= 30
Split Flow Tol= 0.02
Split Flow Ratio= 0.02
Log Output Level= 0
Friction Slope Method= 1
Unsteady Friction Slope Method= 2
Unsteady Bridges Friction Slope Method= 1
Parabolic Critical Depth
Global Vel Dist=  1 , 1 , 1
Global Log Level= 0
CheckData=True
Encroach Param= -1, 0, 0, 0
BEGIN DESCRIPTION:
Multiple Run
END DESCRIPTION:

--- CEDAR BRANCH.f01 (steady flow) ---

Flow Title=Multiple
Number of Profiles=7
Profile Names=10-year,25-year,50-year,1pct_min,100-year,1pct_plu,500-year
River Rch & RM= CEDAR BRANCH,Reach-1,10500
     457     744    1156     866    1575    2862    2216
River Rch & RM= CEDAR BRANCH,Reach-1,9500
     519     853    1394    1030    1921    3583    2725
River Rch & RM= CEDAR BRANCH,Reach-1,7500
     943    1604    3246    2441    4647    8848    6662
River Rch & RM= CEDAR BRANCH,Reach-1,2500
    1060    1821    3607    2651    5177   10108    7412
Boundary for River Rch & Prof#=CEDAR BRANCH,Reach-1,1
Up Type=0
Dn Type=3
Dn Slope=0.005
Boundary for River Rch & Prof#=CEDAR BRANCH,Reach-1,2
Up Type=0
Dn Type=3
Dn Slope=0.005
Boundary for River Rch & Prof#=CEDAR BRANCH,Reach-1,3
Up Type=0
Dn Type=3
Dn Slope=0.005
Boundary for River Rch & Prof#=CEDAR BRANCH,Reach-1,4
Up Type=0
Dn Type=3
Dn Slope=0.005
Boundary for River Rch & Prof#=CEDAR BRANCH,Reach-1,5
Up Type=0
Dn Type=3
Dn Slope=0.005
Boundary for River Rch & Prof#=CEDAR BRANCH,Reach-1,6
Up Type=0
Dn Type=3
Dn Slope=0.005
Boundary for River Rch & Prof#=CEDAR BRANCH,Reach-1,7
Up Type=0
Dn Type=3
Dn Slope=0.005

--- CEDAR BRANCH.g01 (geometry) ---

Geom Title=Existing Conditions

River Reach=CEDAR BRANCH,Reach-1
Reach XY= 30
      2905096.00     10150678.00      2905385.50     10151081.00
      2905526.50     10151610.00      2905520.75     10151711.00
      2905269.25     10152035.00      2905137.25     10152721.00
      2905231.75     10152931.00      2905633.50     10153426.00
      2905858.50     10153852.00      2905815.50     10154266.00
      2905593.50     10154722.00      2905660.50     10155127.00
      2905561.75     10155414.00      2905594.00     10155630.00
      2905885.00     10156172.00      2905992.00     10156796.00
      2906087.75     10157039.00      2906112.00     10157291.00
      2906210.25     10157460.00      2906320.75     10157555.00
      2906242.25     10157765.00      2906243.75     10157881.00
      2906308.50     10157933.00      2906548.50     10158472.00
      2906722.50     10158756.00      2906807.25     10159005.00
      2906851.75     10159349.00      2907112.00     10160008.00
      2907138.00     10160252.00      2906989.25     10160497.00

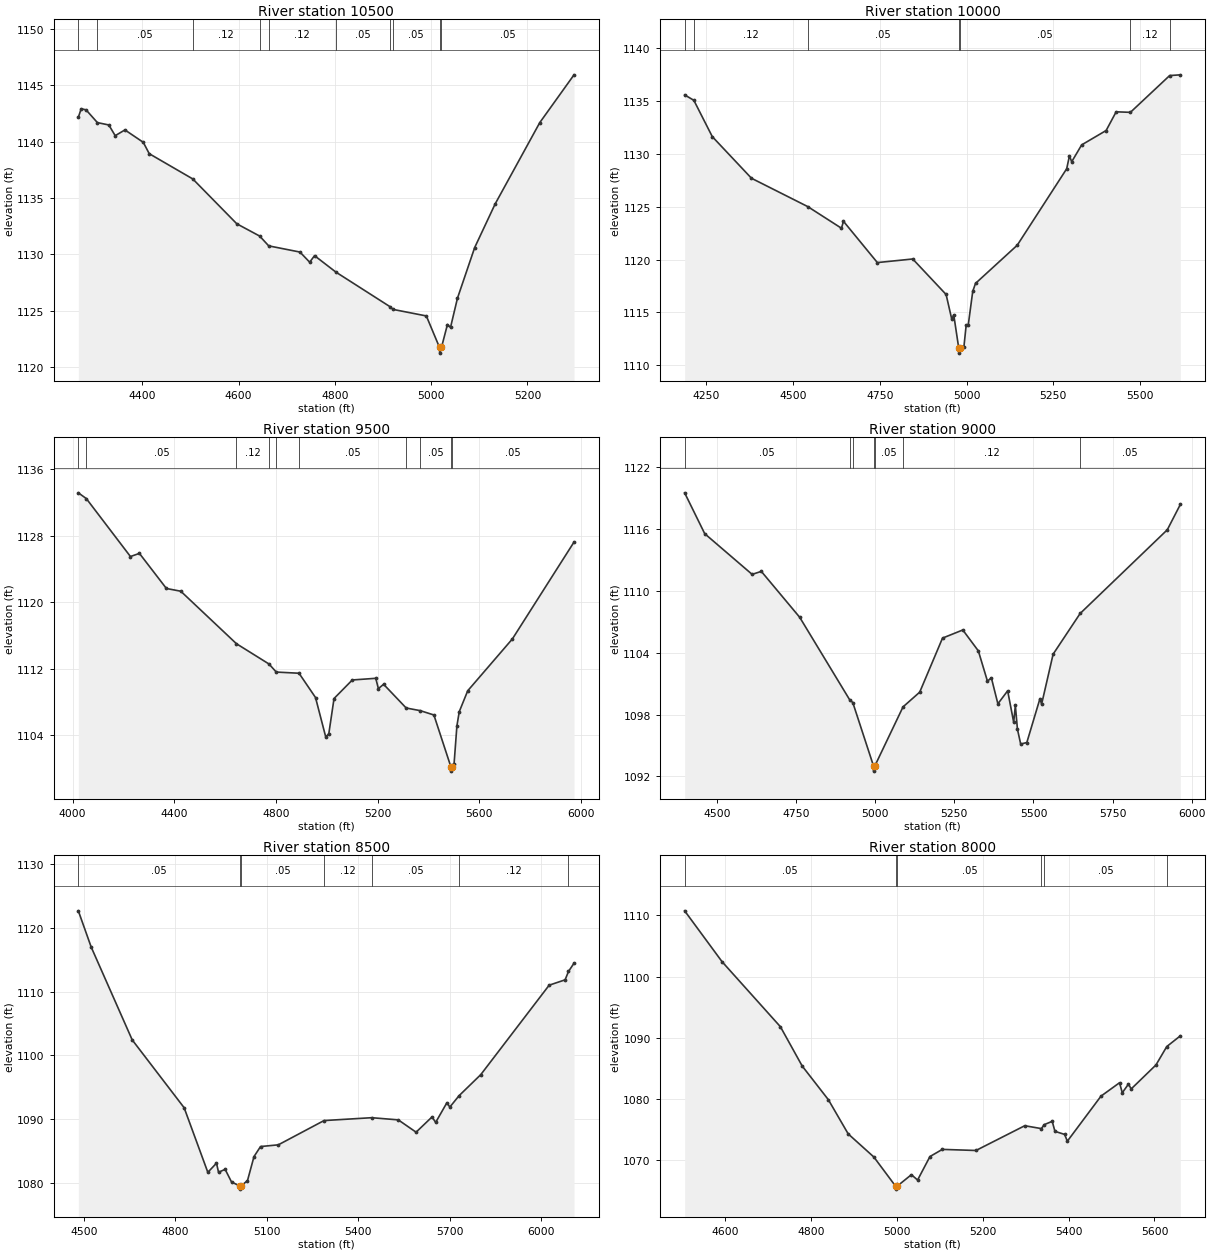
Type RM Length L Ch R = 1,10500,500,500,500
BEGIN DESCRIPTION:
CEDAR BRANCH 21.0
END DESCRIPTION:
XS GIS Cut Line= 3
      2904549.78     10150839.10      2905275.56     10150940.33
      2905505.71     10150753.09
#Sta/Elev= 30
  4267.2 1142.17  4273.2 1142.93  4283.3 1142.83  4306.8 1141.70  4330.5 1141.49
  4343.8 1140.54  4364.0 1141.05  4402.1 1139.95  4414.5 1138.94  4504.9 1136.70
  4596.3 1132.72  4643.8 1131.63  4662.6 1130.76  4727.5 1130.21  4747.7 1129.31
  4757.8 1129.89  4802.2 1128.43  4914.6 1125.36  4920.8 1125.12  4990.0 1124.54
  5017.4 1121.74  5017.7 1121.24  5021.4 1121.74  5033.8 1123.78  5040.2 1123.52
  5054.6 1126.11  5090.4 1130.61  5132.9 1134.48  5225.6 1141.70  5296.7 1145.94
#Mann=10,-1,0
  4267.2    0.12       0  4306.8    0.05       0  4504.9    0.12       0
  4643.8    0.05       0  4662.6    0.12       0  4802.2    0.05       0
  4914.6    0.12       0  4920.8    0.05       0  5017.4    0.05       0
  5021.4    0.05       0
Bank Sta=5017.4,5021.4
Exp/Cntr=0.3,0.1

Type RM Length L Ch R = 1,10000,500,500,500
BEGIN DESCRIPTION:
CEDAR BRANCH 20.0
END DESCRIPTION:
XS GIS Cut Line= 3
      2904755.69     10151003.11      2905472.40     10151385.85
      2905855.68     10150903.11
#Sta/Elev= 30
  4187.5 1135.58  4214.0 1135.07  4267.2 1131.63  4380.2 1127.69  4542.3 1125.01
  4639.6 1122.96  4645.3 1123.62  4743.0 1119.71  4845.0 1120.05  4941.2 1116.69
  4957.5 1114.35  4963.2 1114.77  4977.5 1111.64  4977.7 1111.14  4981.5 1111.64
  4992.4 1111.69  4999.0 1113.77  5004.9 1113.77  5018.0 1116.99  5026.0 1117.74
  5146.2 1121.35  5288.8 1128.59  5296.8 1129.82  5303.2 1129.25  5332.0 1130.85
  5402.5 1132.21  5431.4 1133.98  5472.5 1133.93  5585.6 1137.41  5616.4 1137.48
#Mann=7,-1,0
  4187.5    0.05       0  4214.0    0.12       0  4542.3    0.05       0
  4977.5    0.05       0  4981.5    0.05       0  5472.5    0.12       0
  5585.6    0.05       0
Bank Sta=4977.5,4981.5
Exp/Cntr=0.3,0.1

Type RM Length L Ch R = 1,9500,500,500,500
BEGIN DESCRIPTION:
CEDAR BRANCH 19.0
END DESCRIPTION:
XS GIS Cut Line= 3
      2904705.68     10151153.11      2905407.49     10151833.38
      2906355.67     10152053.11
#Sta/Elev= 30
  4022.6 1133.17  4054.0 1132.48  4227.7 1125.51  4263.0 1125.89  4369.2 1121.67
  4425.8 1121.34  4644.8 1115.03  4772.9 1112.59  4801.6 1111.62  4891.1 1111.48
  4956.0 1108.56  4996.2 1103.82  5008.4 1104.22  5028.9 1108.44  5100.8 1110.67
  5193.1 1110.87  5203.4 1109.63  5224.0 1110.15  5312.8 1107.30  5368.3 1106.98
  5421.9 1106.46  5488.9 1100.21  5489.1 1099.71  5492.9 1100.21  5501.1 1100.51
  5512.4 1105.14  5521.7 1106.86  5555.0 1109.37  5730.9 1115.61  5973.3 1127.25
#Mann=10,-1,0
  4022.6    0.12       0  4054.0    0.05       0  4644.8    0.12       0
  4772.9    0.05       0  4801.6    0.12       0  4891.1    0.05       0
  5312.8    0.12       0  5368.3    0.05       0  5488.9    0.05       0
  5492.9    0.05       0
Bank Sta=5488.9,5492.9
Exp/Cntr=0.3,0.1

Type RM Length L Ch R = 1,9000,500,500,500
BEGIN DESCRIPTION:
CEDAR BRANCH 18.0
END DESCRIPTION:
XS GIS Cut Line= 3
      2904855.69     10151803.12      2905219.29     10152283.55
      2906155.65     10152053.12
#Sta/Elev= 30
  4397.5 1119.54  4461.0 1115.57  4610.8 1111.62  4639.9 1111.91  4761.2 1107.45
  4918.9 1099.45  4929.0 1099.17  4994.5 1093.01  4994.8 1092.51  4998.6 1093.01
  5087.8 1098.75  5140.5 1100.18  5212.6 1105.43  5276.7 1106.22  5325.8 1104.19
  5354.6 1101.25  5367.0 1101.57  5387.6 1099.05  5418.5 1100.31  5437.6 1097.25
  5442.8 1098.89  5449.4 1096.58  5459.7 1095.14  5479.1 1095.29  5520.6 1099.55
  5525.8 1099.01  5562.2 1103.87  5647.6 1107.82  5923.1 1115.95  5964.3 1118.41
#Mann=7,-1,0
  4397.5    0.05       0  4918.9    0.12       0  4929.0    0.05       0
  4994.5    0.05       0  4998.6    0.05       0  5087.8    0.12       0
  5647.6    0.05       0
Bank Sta=4994.5,4998.6
Exp/Cntr=0.3,0.1

Type RM Length L Ch R = 1,8500,500,500,500
BEGIN DESCRIPTION:
CEDAR BRANCH 17.0
END DESCRIPTION:
XS GIS Cut Line= 3
      2904805.70     10153153.10      2905154.00     10152769.95
      2906105.68     10152203.12
#Sta/Elev= 30
  4482.2 1122.66  4524.4 1116.98  4658.9 1102.44  4829.2 1091.81  4906.9 1081.69
  4935.3 1083.13  4942.0 1081.70  4963.6 1082.16  4984.6 1080.18  5011.5 1079.56
  5011.8 1079.06  5015.7 1079.56  5036.9 1080.39  5058.3 1084.16  5079.7 1085.73
  5138.1 1086.00  5287.9 1089.80  5444.0 1090.25  5531.4 1089.91  5589.8 1087.98
  5642.1 1090.37  5654.0 1089.51  5691.0 1092.61  5700.3 1091.91  5730.8 1093.70
  5802.0 1097.00  6026.2 1111.01  6078.5 1111.85  6089.6 1113.16  6107.7 1114.46
#Mann=7,-1,0
  4482.2    0.05       0  5011.5    0.03       0  5015.7    0.05       0
  5287.9    0.12       0  5444.0    0.05       0  5730.8    0.12       0
  6089.6    0.05       0
Bank Sta=5011.5,5015.7
Exp/Cntr=0.3,0.1

Type RM Length L Ch R = 1,8000,500,500,500
BEGIN DESCRIPTION:
CEDAR BRANCH 16.0
END DESCRIPTION:
XS GIS Cut Line= 3
      2904955.70     10153253.11      2905443.38     10153168.88
      2905855.68     10152653.12
#Sta/Elev= 30
  4505.1 1110.76  4592.3 1102.44  4728.3 1091.80  4779.1 1085.37  4840.0 1079.87
  4886.3 1074.27  4946.1 1070.49  4996.5 1065.74  4996.8 1065.24  5000.7 1065.74
  5033.5 1067.60  5048.0 1066.73  5076.8 1070.57  5105.6 1071.74  5184.0 1071.56
  5297.7 1075.61  5336.5 1075.14  5343.2 1075.79  5361.7 1076.33  5368.1 1074.69
  5390.6 1074.19  5397.0 1073.08  5475.4 1080.45  5518.6 1082.64  5525.0 1081.00
  5539.4 1082.42  5545.8 1081.63  5603.5 1085.55  5628.7 1088.56  5660.3 1090.31
#Mann=6,-1,0
  4505.1    0.05       0  4996.5    0.05       0  5000.7    0.05       0
  5336.5    0.12       0  5343.2    0.05       0  5628.7    0.12       0
Bank Sta=4996.5,5000.7
Exp/Cntr=0.3,0.1

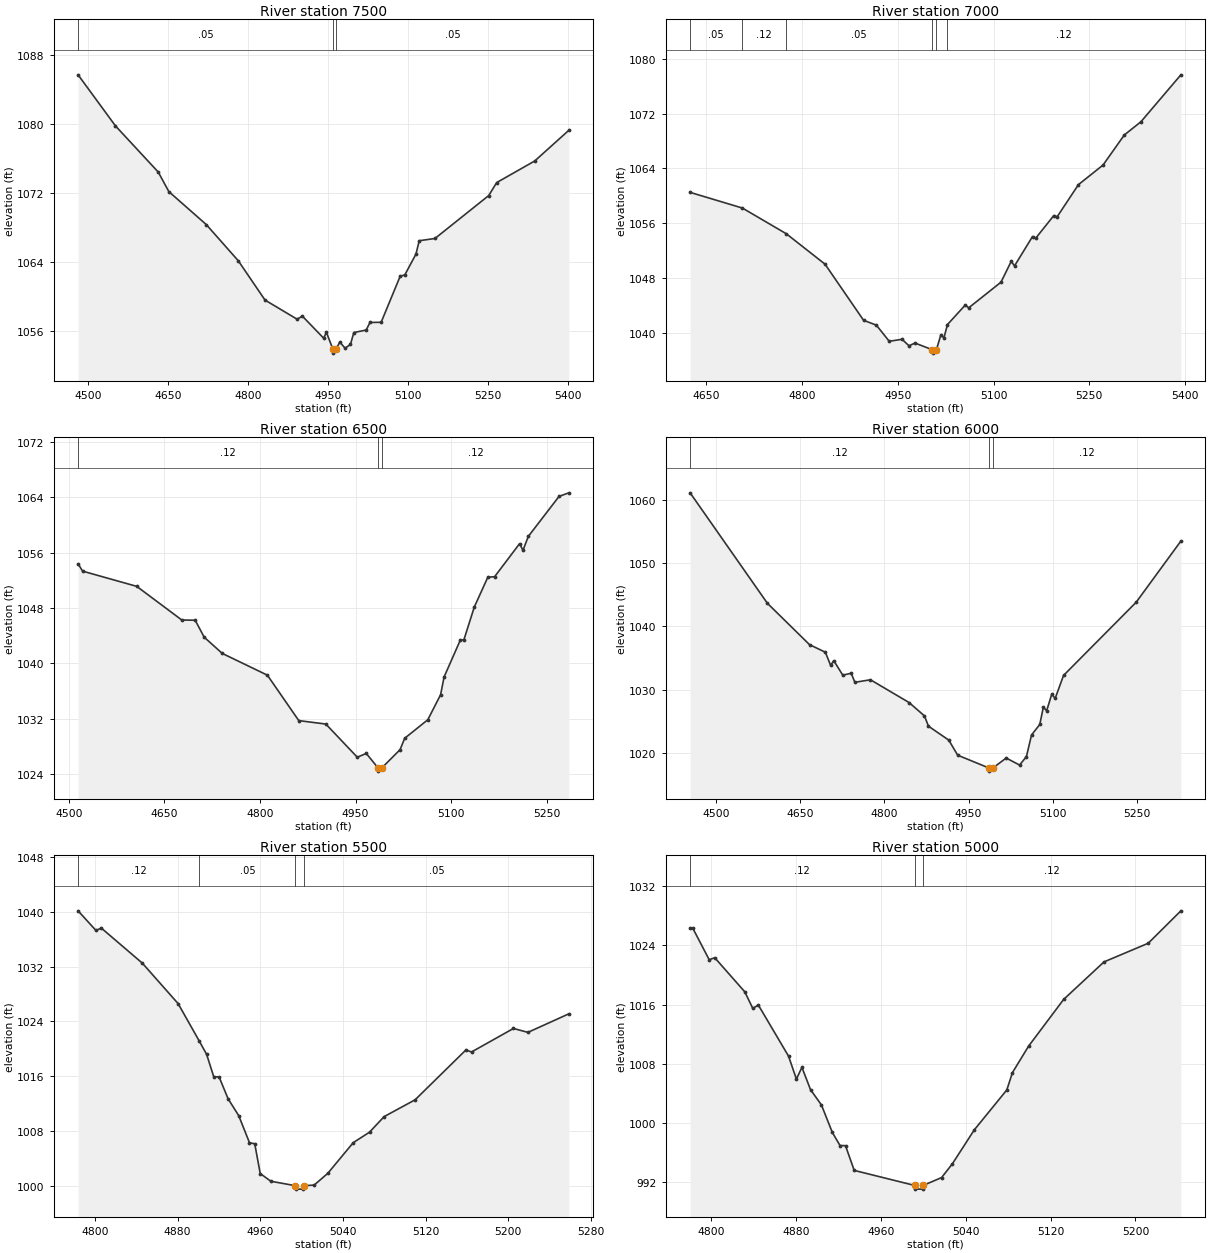
Type RM Length L Ch R = 1,7500,500,500,500
BEGIN DESCRIPTION:
CEDAR BRANCH 15.0
END DESCRIPTION:
XS GIS Cut Line= 3
      2905205.71     10153553.11      2905723.16     10153580.95
      2905955.67     10153253.13
#Sta/Elev= 30
  4481.8 1085.73  4551.9 1079.80  4632.0 1074.45  4652.0 1072.17  4722.1 1068.35
  4782.2 1064.14  4832.3 1059.58  4892.4 1057.36  4902.4 1057.71  4942.3 1055.15
  4947.3 1055.85  4959.3 1053.92  4959.8 1053.42  4965.7 1053.92  4972.5 1054.70
  4982.5 1053.99  4992.5 1054.43  4998.8 1055.81  5021.9 1056.10  5029.1 1056.98
  5050.0 1057.00  5085.7 1062.35  5094.4 1062.50  5115.3 1064.92  5121.4 1066.47
  5150.9 1066.73  5251.8 1071.72  5266.6 1073.22  5338.0 1075.73  5401.9 1079.29
#Mann=3,-1,0
  4481.8    0.05       0  4959.3    0.05       0  4965.7    0.05       0
Bank Sta=4959.3,4965.7
Exp/Cntr=0.3,0.1

Type RM Length L Ch R = 1,7000,500,500,500
BEGIN DESCRIPTION:
CEDAR BRANCH 14.0
END DESCRIPTION:
XS GIS Cut Line= 3
      2905455.72     10154003.12      2905828.51     10154041.90
      2906205.65     10154153.10
#Sta/Elev= 30
  4625.2 1060.51  4707.0 1058.22  4775.7 1054.47  4836.3 1050.03  4896.6 1041.84
  4916.7 1041.12  4936.8 1038.77  4956.9 1039.06  4967.7 1038.11  4977.1 1038.51
  5004.2 1037.54  5004.7 1037.04  5010.7 1037.54  5017.3 1039.63  5022.5 1039.30
  5027.9 1041.21  5055.9 1044.07  5061.1 1043.65  5111.7 1047.40  5127.7 1050.44
  5132.9 1049.78  5161.0 1054.06  5166.2 1053.84  5194.3 1057.12  5199.6 1056.95
  5232.9 1061.64  5271.4 1064.50  5304.7 1068.89  5330.7 1070.82  5393.2 1077.67
#Mann=6,-1,0
  4625.2    0.05       0  4707.0    0.12       0  4775.7    0.05       0
  5004.2    0.05       0  5010.7    0.05       0  5027.9    0.12       0
Bank Sta=5004.2,5010.7
Exp/Cntr=0.3,0.1

Type RM Length L Ch R = 1,6500,500,500,500
BEGIN DESCRIPTION:
CEDAR BRANCH 13.0
END DESCRIPTION:
XS GIS Cut Line= 3
      2905355.69     10154153.11      2905686.82     10154508.44
      2905955.64     10154603.10
#Sta/Elev= 30
  4514.3 1054.40  4521.4 1053.34  4606.4 1051.14  4677.2 1046.27  4698.2 1046.24
  4712.4 1043.78  4740.7 1041.44  4811.6 1038.29  4860.9 1031.72  4903.4 1031.22
  4952.8 1026.42  4966.9 1026.97  4985.1 1024.91  4985.6 1024.41  4991.7 1024.91
  5020.0 1027.52  5027.2 1029.16  5063.5 1031.84  5083.6 1035.46  5089.1 1038.03
  5114.8 1043.41  5120.1 1043.38  5136.6 1048.16  5157.8 1052.47  5168.4 1052.53
  5207.7 1057.32  5213.0 1056.35  5221.4 1058.37  5269.6 1064.15  5285.0 1064.67
#Mann=3,-1,0
  4514.3    0.12       0  4985.1    0.07       0  4991.7    0.12       0
Bank Sta=4985.1,4991.7
Exp/Cntr=0.3,0.1

Type RM Length L Ch R = 1,6000,500,500,500
BEGIN DESCRIPTION:
CEDAR BRANCH 12.0
END DESCRIPTION:
XS GIS Cut Line= 3
      2905155.68     10155253.11      2905631.45     10154984.21
      2905905.66     10154803.13
#Sta/Elev= 30
  4453.5 1061.09  4591.3 1043.64  4666.4 1037.11  4694.7 1035.91  4704.0 1033.84
  4709.7 1034.58  4725.7 1032.29  4740.7 1032.59  4747.3 1031.16  4775.1 1031.56
  4844.0 1027.96  4871.4 1025.85  4878.5 1024.23  4914.7 1022.03  4930.6 1019.65
  4986.2 1017.63  4986.7 1017.13  4993.5 1017.63  5017.1 1019.20  5041.0 1018.09
  5053.2 1019.43  5062.3 1022.84  5077.0 1024.50  5083.3 1027.21  5089.3 1026.68
  5098.4 1029.29  5104.4 1028.61  5119.4 1032.25  5248.9 1043.81  5328.6 1053.47
#Mann=3,-1,0
  4453.5    0.12       0  4986.2    0.07       0  4993.5    0.12       0
Bank Sta=4986.2,4993.5
Exp/Cntr=0.3,0.1

Type RM Length L Ch R = 1,5500,500,500,500
BEGIN DESCRIPTION:
CEDAR BRANCH 11.0
END DESCRIPTION:
XS GIS Cut Line= 3
      2905355.64     10155403.10      2905564.31     10155460.04
      2905805.68     10155553.11
#Sta/Elev= 30
  4783.7 1040.17  4801.0 1037.30  4806.2 1037.65  4845.9 1032.52  4880.5 1026.61
  4901.0 1021.13  4908.1 1019.19  4915.0 1015.92  4920.2 1015.88  4928.9 1012.69
  4939.2 1010.22  4949.6 1006.27  4954.7 1006.11  4960.0 1001.76  4970.3 1000.63
  4994.1  999.98  4994.6  999.48  5001.7  999.48  5002.2  999.98  5012.2 1000.07
  5025.4 1001.79  5050.0 1006.27  5065.8 1007.81  5079.9 1010.08  5109.9 1012.54
  5159.1 1019.83  5164.5 1019.53  5205.1 1022.97  5219.1 1022.40  5258.7 1025.11
#Mann=4,-1,0
  4783.7    0.12       0  4901.0    0.05       0  4994.1    0.05       0
  5002.2    0.05       0
Bank Sta=4994.1,5002.2
Exp/Cntr=0.3,0.1

Type RM Length L Ch R = 1,5000,437,437,437
BEGIN DESCRIPTION:
CEDAR BRANCH 10.0
END DESCRIPTION:
XS GIS Cut Line= 3
      2905555.66     10155853.11      2905768.82     10155906.74
      2906005.72     10155853.10
#Sta/Elev= 30
  4780.2 1026.31  4782.8 1026.31  4798.2 1022.07  4803.4 1022.35  4831.8 1017.73
  4839.3 1015.49  4844.5 1015.96  4873.0 1009.05  4880.4 1005.95  4885.6 1007.54
  4893.7 1004.53  4904.0 1002.46  4914.3  998.74  4921.5  996.98  4926.7  996.96
  4934.9  993.62  4991.8  991.59  4992.3  991.09  4999.4  991.09  4999.9  991.59
  5017.3  992.65  5027.5  994.52  5048.1  999.09  5078.8 1004.49  5084.1 1006.83
  5099.3 1010.40  5132.4 1016.72  5170.4 1021.78  5212.1 1024.30  5242.9 1028.68
#Mann=3,-1,0
  4780.2    0.12       0  4991.8    0.07       0  4999.9    0.12       0
Bank Sta=4991.8,4999.9
Exp/Cntr=0.3,0.1

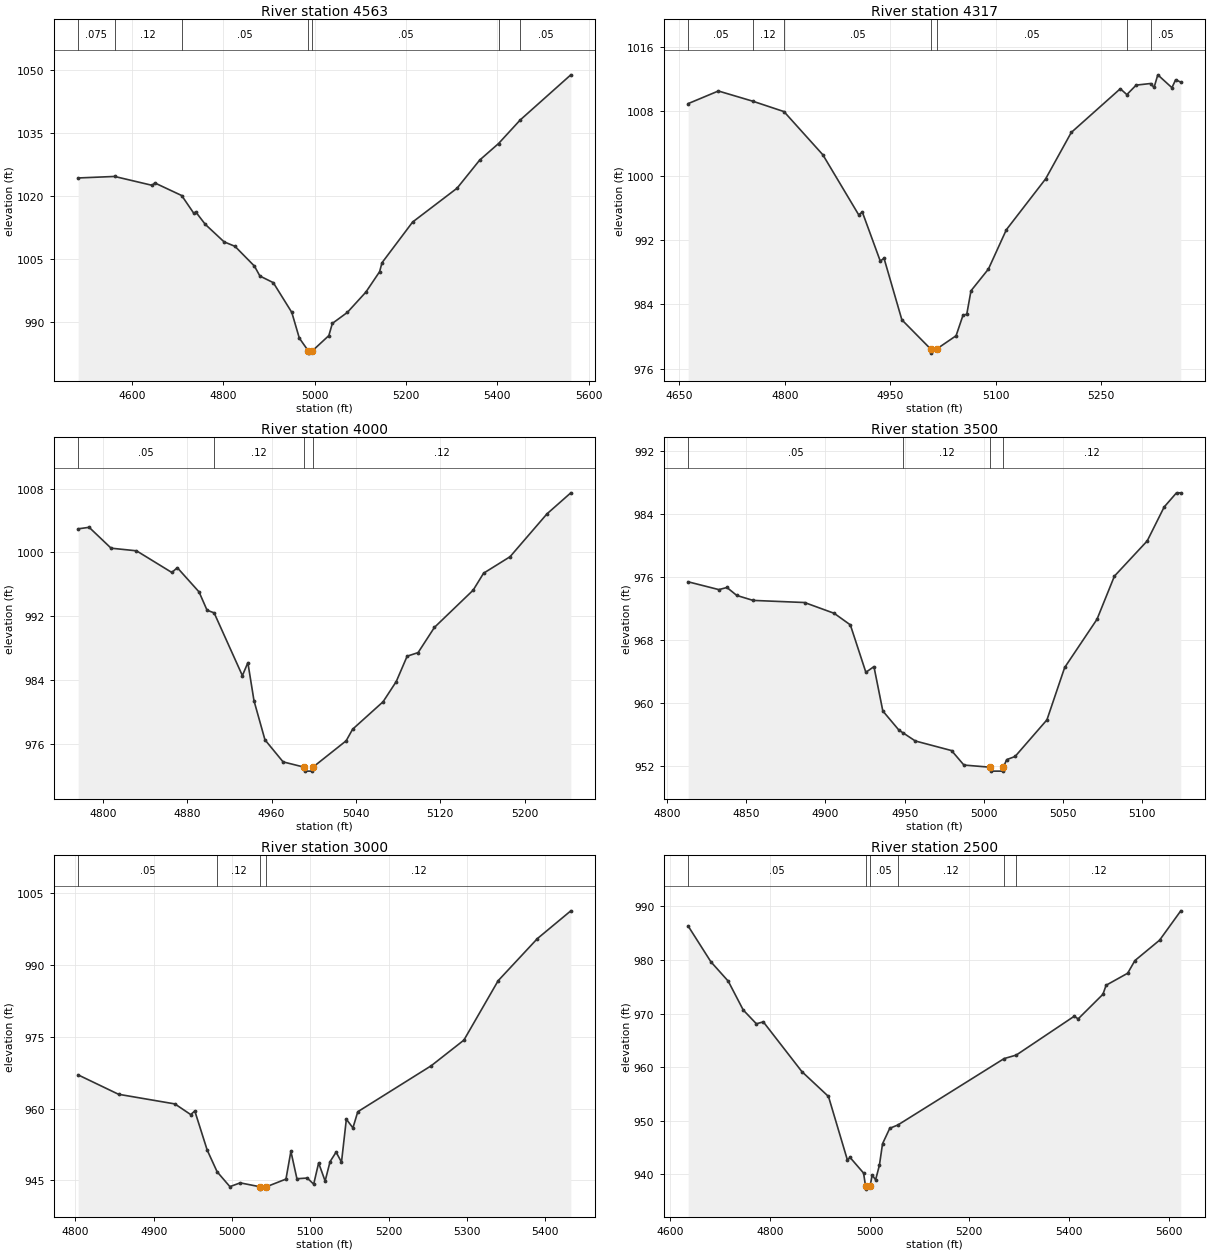
Type RM Length L Ch R = 1,4563,246,246,246
BEGIN DESCRIPTION:
Mapping XS 5d6bcb6d
END DESCRIPTION:
XS GIS Cut Line= 4
      2905414.64     10156435.34      2905803.55     10156345.06
      2906150.77     10156254.78      2906428.52     10156095.08
#Sta/Elev= 30
  4482.5 1024.33  4562.2 1024.69  4644.9 1022.56  4650.1 1023.15  4709.1 1020.14
  4735.3 1015.95  4740.5 1016.14  4760.7 1013.27  4801.8 1009.10  4825.8 1008.02
  4868.4 1003.30  4880.3 1000.94  4909.6  999.36  4950.1  992.27  4966.6  986.13
  4986.5  983.05  4987.0  982.55  4994.7  983.05  5031.2  986.73  5038.9  989.64
  5071.7  992.26  5112.3  997.11  5142.3 1001.97  5147.6 1004.11  5214.6 1013.82
  5311.9 1021.89  5361.5 1028.61  5402.7 1032.54  5450.1 1038.16  5560.9 1048.93
#Mann=7,-1,0
  4482.5   0.075       0  4562.2    0.12       0  4709.1    0.05       0
  4986.5    0.05       0  4994.7    0.05       0  5402.7    0.12       0
  5450.1    0.05       0
Bank Sta=4986.5,4994.7
Exp/Cntr=0.3,0.1

Type RM Length L Ch R = 1,4317,317,317,317
BEGIN DESCRIPTION:
Mapping XS c71ed273
END DESCRIPTION:
XS GIS Cut Line= 2
      2905636.90     10156671.45      2906296.62     10156435.33
#Sta/Elev= 30
  4662.6 1008.96  4705.6 1010.53  4754.2 1009.27  4798.9 1007.97  4854.2 1002.60
  4905.1  995.15  4910.4  995.47  4935.9  989.38  4941.2  989.74  4966.6  982.08
  5007.7  978.44  5008.2  977.94  5015.9  978.44  5043.7  980.10  5053.6  982.66
  5058.9  982.77  5064.9  985.69  5089.7  988.39  5115.2  993.28  5171.1  999.61
  5207.5 1005.37  5277.3 1010.81  5286.6 1010.08  5299.8 1011.26  5320.3 1011.46
  5325.3 1010.97  5330.6 1012.54  5350.7 1010.94  5356.0 1011.93  5363.3 1011.63
#Mann=7,-1,0
  4662.6    0.05       0  4754.2    0.12       0  4798.9    0.05       0
  5007.7    0.03       0  5015.9    0.05       0  5286.6    0.12       0
  5320.3    0.05       0
Bank Sta=5007.7,5015.9
Exp/Cntr=0.3,0.1

Type RM Length L Ch R = 1,4000,500,500,500
BEGIN DESCRIPTION:
CEDAR BRANCH 8.0
END DESCRIPTION:
XS GIS Cut Line= 3
      2905805.72     10156803.12      2906020.04     10156865.80
      2906255.65     10156803.12
#Sta/Elev= 30
  4776.7 1002.97  4787.1 1003.16  4807.9 1000.54  4832.0 1000.21  4865.5  997.49
  4870.7  998.09  4891.3  995.05  4898.9  992.75  4905.6  992.42  4932.4  984.54
  4937.6  986.17  4943.4  981.39  4953.8  976.48  4971.0  973.71  4990.9  973.05
  4991.4  972.55  4998.8  972.55  4999.3  973.05  5030.8  976.36  5036.9  977.81
  5065.8  981.26  5078.3  983.80  5088.6  986.98  5099.0  987.43  5114.5  990.60
  5151.2  995.27  5161.1  997.40  5186.2  999.47  5221.2 1004.85  5243.8 1007.49
#Mann=4,-1,0
  4776.7    0.05       0  4905.6    0.12       0  4990.9    0.07       0
  4999.3    0.12       0
Bank Sta=4990.9,4999.3
Exp/Cntr=0.3,0.1

Type RM Length L Ch R = 1,3500,500,500,500
BEGIN DESCRIPTION:
CEDAR BRANCH 7.0
END DESCRIPTION:
XS GIS Cut Line= 3
      2905955.65     10157303.10      2906138.03     10157343.06
      2906255.73     10157303.10
#Sta/Elev= 30
  4813.3  975.42  4832.7  974.43  4837.8  974.70  4844.0  973.69  4854.3  973.06
  4886.8  972.79  4905.5  971.42  4915.7  969.95  4925.5  963.93  4930.6  964.65
  4936.2  959.02  4946.4  956.58  4949.2  956.21  4956.7  955.21  4979.6  953.99
  4987.4  952.15  5003.8  951.88  5004.3  951.38  5011.8  951.38  5012.3  951.88
  5014.4  952.84  5019.7  953.24  5039.8  957.89  5051.0  964.54  5071.4  970.66
  5082.4  976.14  5103.1  980.61  5113.8  984.92  5121.6  986.72  5124.3  986.72
#Mann=4,-1,0
  4813.3    0.05       0  4949.2    0.12       0  5003.8    0.07       0
  5012.3    0.12       0
Bank Sta=5003.8,5012.3
Exp/Cntr=0.3,0.1

Type RM Length L Ch R = 1,3000,500,500,500
BEGIN DESCRIPTION:
CEDAR BRANCH 6.0
END DESCRIPTION:
XS GIS Cut Line= 3
      2906055.67     10157703.11      2906246.63     10157749.42
      2906505.69     10157403.10
#Sta/Elev= 30
  4803.5  967.03  4855.0  962.98  4927.0  960.96  4947.2  958.73  4952.4  959.49
  4968.2  951.32  4980.9  946.77  4997.2  943.66  5010.4  944.45  5035.4  943.64
  5035.9  943.14  5043.9  943.64  5068.8  945.24  5075.1  951.05  5082.8  945.31
  5095.9  945.46  5104.2  944.18  5110.5  948.62  5118.8  944.83  5125.1  948.89
  5132.8  950.88  5139.7  948.79  5145.9  957.76  5154.3  955.95  5160.5  959.33
  5254.3  968.95  5296.0  974.31  5339.7  986.73  5389.8  995.54  5432.5 1001.35
#Mann=4,-1,0
  4803.5    0.05       0  4980.9    0.12       0  5035.4    0.07       0
  5043.9    0.12       0
Bank Sta=5035.4,5043.9
Exp/Cntr=0.3,0.1

Type RM Length L Ch R = 1,2500,500,500,500
BEGIN DESCRIPTION:
CEDAR BRANCH 5.0
END DESCRIPTION:
XS GIS Cut Line= 3
      2906055.69     10158153.11      2906417.74     10158192.61
      2906805.69     10157703.10
#Sta/Elev= 30
  4635.8  986.34  4681.5  979.66  4716.3  976.05  4746.4  970.67  4772.8  968.10
  4786.7  968.46  4864.2  959.17  4917.5  954.54  4955.6  942.65  4960.6  943.19
  4987.9  940.26  4992.0  937.76  4992.5  937.26  5000.9  937.76  5005.2  939.87
  5012.1  939.00  5019.7  941.71  5026.0  945.73  5040.5  948.61  5056.7  949.22
  5270.0  961.61  5294.3  962.26  5410.6  969.50  5418.7  969.02  5468.4  973.61
  5474.7  975.29  5518.0  977.53  5532.5  979.89  5582.1  983.70  5624.6  989.17
#Mann=6,-1,0
  4635.8    0.05       0  4992.0    0.03       0  5000.9    0.05       0
  5056.7    0.12       0  5270.0    0.05       0  5294.3    0.12       0
Bank Sta=4992,5000.9
Exp/Cntr=0.3,0.1

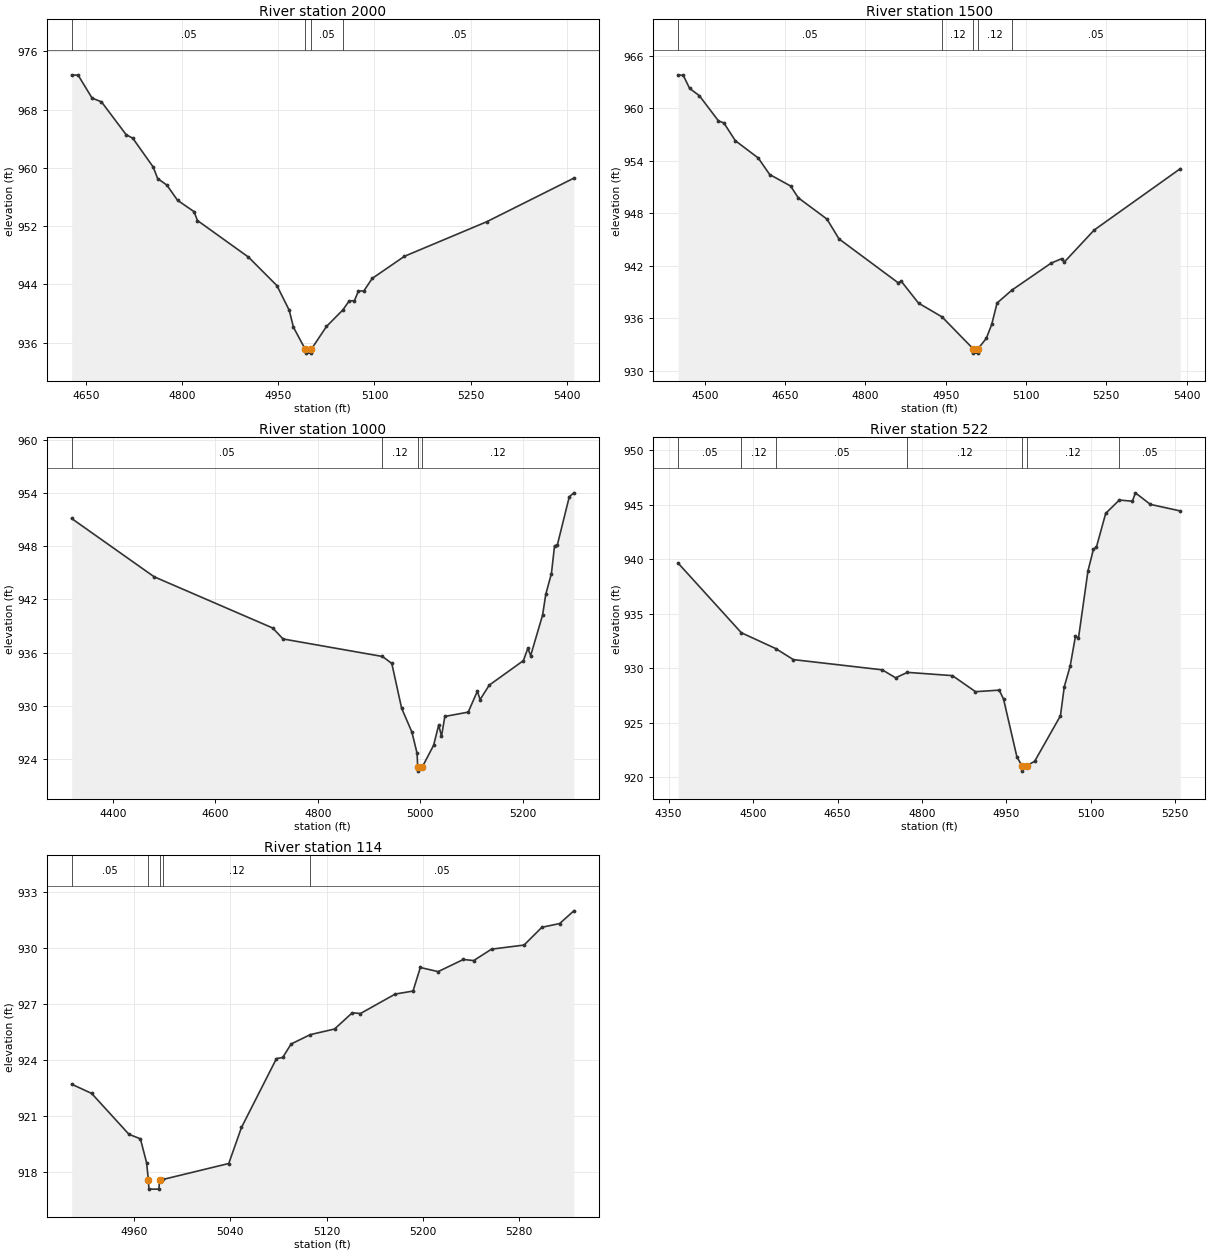
Type RM Length L Ch R = 1,2000,500,500,500
BEGIN DESCRIPTION:
CEDAR BRANCH 4.0
END DESCRIPTION:
XS GIS Cut Line= 3
      2906305.69     10158753.11      2906656.67     10158629.83
      2906905.69     10158303.11
#Sta/Elev= 30
  4628.0  972.77  4638.2  972.71  4659.8  969.58  4674.5  969.06  4712.8  964.57
  4723.4  964.05  4755.2  960.10  4762.1  958.52  4776.4  957.63  4793.1  955.54
  4818.8  953.98  4824.1  952.76  4903.6  947.74  4948.0  943.82  4967.2  940.43
  4973.7  938.11  4992.3  935.05  4992.8  934.55  5000.8  934.55  5001.3  935.05
  5025.2  938.21  5050.7  940.48  5060.6  941.72  5068.8  941.75  5075.1  943.10
  5083.4  943.08  5096.5  944.81  5146.8  947.85  5274.7  952.58  5410.8  958.58
#Mann=4,-1,0
  4628.0    0.05       0  4992.3    0.07       0  5001.3    0.05       0
  5050.7    0.05       0
Bank Sta=4992.3,5001.3
Exp/Cntr=0.3,0.1

Type RM Length L Ch R = 1,1500,500,500,500
BEGIN DESCRIPTION:
CEDAR BRANCH 3.0
END DESCRIPTION:
XS GIS Cut Line= 3
      2906305.70     10158903.12      2906819.84     10159097.88
      2907205.65     10159053.12
#Sta/Elev= 30
  4450.2  963.81  4459.9  963.74  4471.6  962.27  4490.1  961.41  4525.6  958.54
  4535.7  958.31  4557.1  956.28  4599.9  954.30  4621.3  952.41  4660.3  951.10
  4674.7  949.75  4728.2  947.32  4750.8  945.05  4860.7  940.06  4867.2  940.20
  4899.3  937.71  4943.3  936.13  5001.3  932.49  5001.8  931.99  5010.0  931.99
  5010.5  932.49  5026.0  933.68  5036.1  935.28  5046.1  937.72  5073.9  939.20
  5146.8  942.27  5166.7  942.79  5171.8  942.41  5227.4  946.06  5388.4  953.08
#Mann=5,-1,0
  4450.2    0.05       0  4943.3    0.12       0  5001.3    0.07       0
  5010.5    0.12       0  5073.9    0.05       0
Bank Sta=5001.3,5010.5
Exp/Cntr=0.3,0.1

Type RM Length L Ch R = 1,1000,478,478,478
BEGIN DESCRIPTION:
CEDAR BRANCH 2.0
END DESCRIPTION:
XS GIS Cut Line= 3
      2906255.69     10159653.11      2906932.15     10159581.84
      2907205.67     10159703.11
#Sta/Elev= 30
  4319.8  951.15  4480.7  944.56  4711.9  938.77  4732.1  937.53  4926.0  935.55
  4944.2  934.76  4963.3  929.71  4983.4  927.00  4993.5  924.60  4994.7  923.09
  4995.2  922.59  5003.9  923.09  5025.7  925.51  5035.7  927.81  5041.1  926.52
  5047.6  928.77  5093.2  929.26  5111.0  931.62  5116.4  930.68  5134.2  932.31
  5200.8  935.08  5209.5  936.47  5215.0  935.65  5238.3  940.24  5244.5  942.59
  5255.5  944.93  5261.6  948.07  5267.0  948.15  5290.3  953.60  5299.2  954.05
#Mann=4,-1,0
  4319.8    0.05       0  4926.0    0.12       0  4994.7    0.07       0
  5003.9    0.12       0
Bank Sta=4994.7,5003.9
Exp/Cntr=0.3,0.1

Type RM Length L Ch R = 1,522,408,408,408
BEGIN DESCRIPTION:
Mapping XS cc19a252
END DESCRIPTION:
XS GIS Cut Line= 3
      2906493.09     10159987.80      2907001.88     10160058.72
      2907361.67     10159941.86
#Sta/Elev= 30
  4366.8  939.63  4479.1  933.25  4540.2  931.80  4571.4  930.79  4729.5  929.85
  4753.1  929.12  4774.1  929.62  4854.1  929.32  4895.0  927.85  4937.1  927.99
  4944.8  927.18  4968.6  921.87  4977.4  921.07  4977.9  920.57  4986.6  921.07
  5000.2  921.48  5045.9  925.64  5052.7  928.30  5063.2  930.20  5072.6  932.94
  5077.9  932.74  5094.8  938.92  5104.6  940.91  5109.8  941.10  5126.3  944.19
  5150.5  945.41  5173.7  945.30  5179.0  946.07  5205.7  945.01  5258.8  944.41
#Mann=7,-1,0
  4366.8    0.05       0  4479.1    0.12       0  4540.2    0.05       0
  4774.1    0.12       0  4977.4    0.07       0  4986.6    0.12       0
  5150.5    0.05       0
Bank Sta=4977.4,4986.6
Exp/Cntr=0.3,0.1

Type RM Length L Ch R = 1,114,0,0,0
BEGIN DESCRIPTION:
CEDAR BRANCH 1.0
END DESCRIPTION:
XS GIS Cut Line= 3
      2906969.70     10160381.65      2907164.49     10160435.70
      2907340.90     10160311.68
#Sta/Elev= 30
  4907.9  922.72  4924.5  922.23  4955.6  920.04  4965.1  919.80  4970.3  918.51
  4971.7  917.61  4972.2  917.11  4980.5  917.11  4981.0  917.61  4984.0  917.63
  5038.6  918.48  5049.2  920.41  5078.3  924.09  5083.5  924.15  5090.5  924.87
  5106.4  925.37  5126.6  925.67  5141.4  926.54  5148.2  926.50  5177.1  927.54
  5191.9  927.70  5198.0  928.96  5212.8  928.74  5233.8  929.39  5242.4  929.33
  5257.2  929.94  5284.3  930.16  5299.1  931.11  5313.9  931.31  5325.7  931.99
#Mann=5,-1,0
  4907.9    0.05       0  4971.7    0.07       0  4981.0    0.05       0
  4984.0    0.12       0  5106.4    0.05       0
Bank Sta=4971.7,4981
Exp/Cntr=0.3,0.1

Chan Stop Cuts=-1