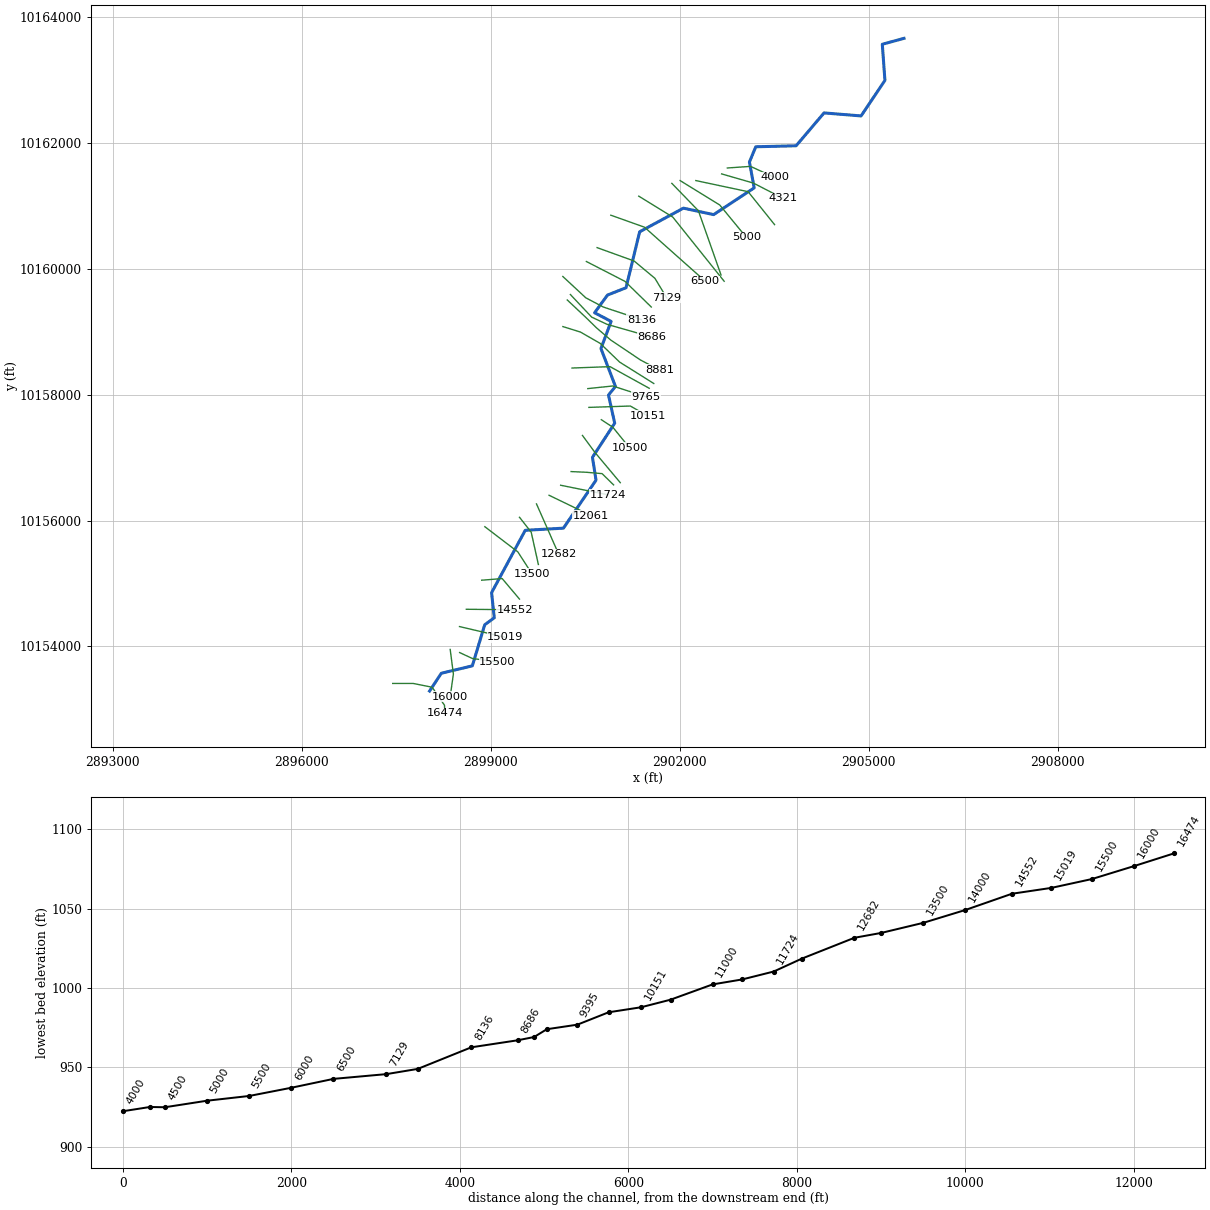
--- DRY BRANCH.prj (project) ---

Proj Title=DRY BRANCH Base Level Engineering
Current Plan=p01
Default Exp/Contr=0.3,0.1
English Units
Geom File=g01
Flow File=f01
Plan File=p01
Y Axis Title=Elevation
X Axis Title(PF)=Main Channel Distance
X Axis Title(XS)=Station
BEGIN DESCRIPTION:
DRY BRANCH
END DESCRIPTION:
DSS Export Rating Curves= 0
DSS Export Rating Curve Sorted= 0
DSS Export Volume Flow Curves= 0
DXF OffsetX= 0
DXF OffsetY= 0
DXF ScaleX= 1
DXF ScaleY= 10

--- DRY BRANCH.p01 (plan) ---

Plan Title=Multiple Run
Short Identifier=Multiple
Geom File=g01
Flow File=f01
Subcritical Flow
K Sum by GR= 0
Std Step Tol= 0.01
Critical Tol= 0.01
Num of Std Step Trials= 20
Max Error Tol= 0.3
Flow Tol Ratio= 0.001
Split Flow NTrial= 30
Split Flow Tol= 0.02
Split Flow Ratio= 0.02
Log Output Level= 0
Friction Slope Method= 1
Unsteady Friction Slope Method= 2
Unsteady Bridges Friction Slope Method= 1
Parabolic Critical Depth
Global Vel Dist=  1 , 1 , 1
Global Log Level= 0
CheckData=True
Encroach Param= -1, 0, 0, 0
BEGIN DESCRIPTION:
Multiple Run
END DESCRIPTION:

--- DRY BRANCH.f01 (steady flow) ---

Flow Title=Multiple
Number of Profiles=7
Profile Names=10-year,25-year,50-year,1pct_min,100-year,1pct_plu,500-year
River Rch & RM= DRY BRANCH,Reach-1,16474
     492     807    1377    1025    1907    3548    2726
River Rch & RM= DRY BRANCH,Reach-1,5000
     534     883    1474    1076    2043    3878    2916
River Rch & RM= DRY BRANCH,Reach-1,3500
     979    1667    3223    2422    4588    8689    6515
Boundary for River Rch & Prof#=DRY BRANCH,Reach-1,1
Up Type=0
Dn Type=3
Dn Slope=0.005
Boundary for River Rch & Prof#=DRY BRANCH,Reach-1,2
Up Type=0
Dn Type=3
Dn Slope=0.005
Boundary for River Rch & Prof#=DRY BRANCH,Reach-1,3
Up Type=0
Dn Type=3
Dn Slope=0.005
Boundary for River Rch & Prof#=DRY BRANCH,Reach-1,4
Up Type=0
Dn Type=3
Dn Slope=0.005
Boundary for River Rch & Prof#=DRY BRANCH,Reach-1,5
Up Type=0
Dn Type=3
Dn Slope=0.005
Boundary for River Rch & Prof#=DRY BRANCH,Reach-1,6
Up Type=0
Dn Type=3
Dn Slope=0.005
Boundary for River Rch & Prof#=DRY BRANCH,Reach-1,7
Up Type=0
Dn Type=3
Dn Slope=0.005

--- DRY BRANCH.g01 (geometry) ---

Geom Title=Existing Conditions

River Reach=DRY BRANCH,Reach-1
Reach XY= 30
      2898028.50     10153292.00      2898215.00     10153575.00
      2898707.00     10153692.00      2898903.75     10154345.00
      2899055.25     10154456.00      2899013.00     10154855.00
      2899547.00     10155846.00      2900153.75     10155880.00
      2900670.75     10156643.00      2900614.50     10157006.00
      2900967.50     10157548.00      2900869.00     10157995.00
      2900979.25     10158132.00      2900749.50     10158734.00
      2900910.75     10159165.00      2900648.50     10159303.00
      2900853.00     10159584.00      2901147.50     10159700.00
      2901363.75     10160589.00      2902059.00     10160965.00
      2902538.25     10160862.00      2903182.50     10161287.00
      2903106.50     10161698.00      2903207.50     10161940.00
      2903848.00     10161956.00      2904291.50     10162478.00
      2904879.25     10162430.00      2905258.00     10162995.00
      2905216.25     10163569.00      2905561.00     10163663.00

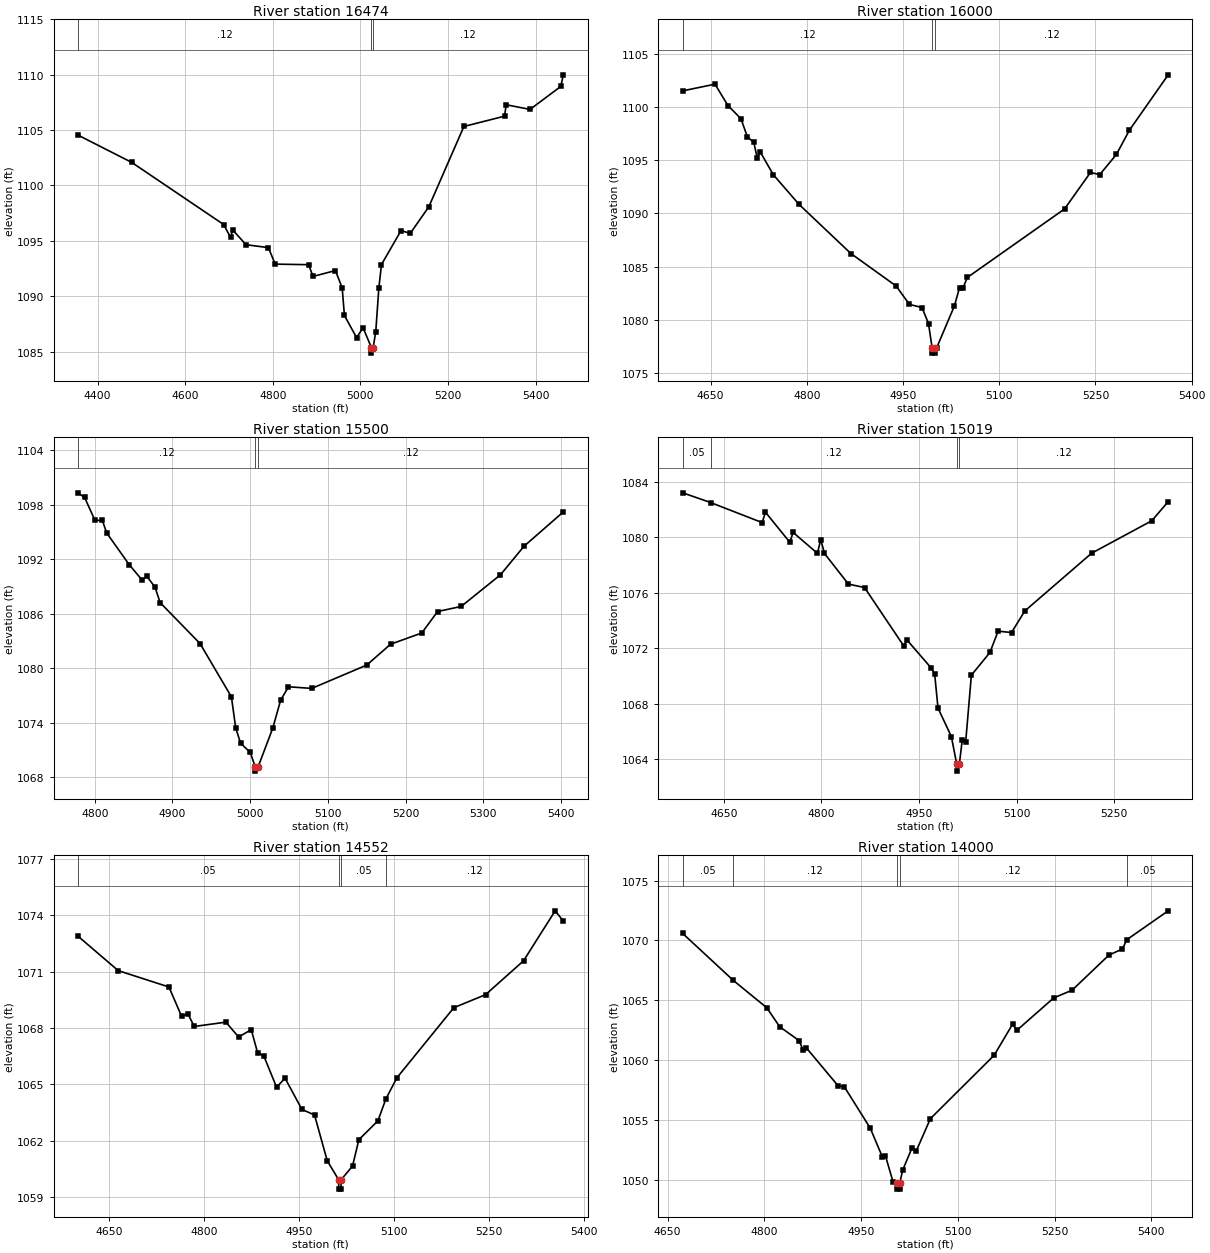
Type RM Length L Ch R = 1,16474,474,474,474
BEGIN DESCRIPTION:
Mapping XS b584d6c4
END DESCRIPTION:
XS GIS Cut Line= 5
      2897442.72     10153412.61      2897768.59     10153412.61
      2898069.40     10153352.45      2898264.93     10153066.68
      2898269.91     10152937.17
#Sta/Elev= 30
  4355.0 1104.55  4478.0 1102.08  4688.1 1096.47  4703.6 1095.32  4708.7 1095.98
  4739.1 1094.65  4790.1 1094.39  4805.6 1092.90  4881.9 1092.85  4892.1 1091.79
  4943.1 1092.32  4958.6 1090.76  4963.7 1088.27  4991.4 1086.27  5006.3 1087.16
  5025.3 1085.37  5025.5 1084.87  5029.3 1085.37  5035.3 1086.82  5042.2 1090.71
  5048.3 1092.86  5093.0 1095.93  5114.0 1095.67  5156.5 1098.08  5236.5 1105.32
  5329.3 1106.25  5333.0 1107.28  5387.5 1106.86  5457.6 1108.93  5463.5 1109.98
#Mann=3,-1,0
  4355.0    0.12       0  5025.3    0.07       0  5029.3    0.12       0
Bank Sta=5025.3,5029.3
Exp/Cntr=0.3,0.1

Type RM Length L Ch R = 1,16000,500,500,500
BEGIN DESCRIPTION:
DRY BRANCH 32.0
END DESCRIPTION:
XS GIS Cut Line= 3
      2898355.68     10153953.11      2898406.43     10153563.00
      2898355.69     10153203.16
#Sta/Elev= 30
  4606.6 1101.55  4657.0 1102.18  4677.2 1100.16  4697.4 1098.93  4707.4 1097.23
  4717.5 1096.69  4722.7 1095.25  4727.8 1095.77  4747.8 1093.66  4788.1 1090.85
  4868.8 1086.23  4939.4 1083.17  4960.0 1081.44  4979.7 1081.14  4989.8 1079.63
  4995.4 1077.35  4995.7 1076.85  4999.2 1076.85  4999.4 1077.35  5002.5 1077.35
  5030.2 1081.30  5038.2 1083.03  5043.2 1082.94  5050.4 1083.98  5201.9 1090.43
  5242.3 1093.87  5256.7 1093.66  5282.7 1095.56  5302.9 1097.84  5363.4 1103.06
#Mann=3,-1,0
  4606.6    0.12       0  4995.4    0.07       0  4999.4    0.12       0
Bank Sta=4995.4,4999.4
Exp/Cntr=0.3,0.1

Type RM Length L Ch R = 1,15500,481,481,481
BEGIN DESCRIPTION:
DRY BRANCH 31.0
END DESCRIPTION:
XS GIS Cut Line= 3
      2898505.68     10153903.11      2898706.96     10153809.92
      2899105.73     10153753.10
#Sta/Elev= 30
  4778.2 1099.31  4786.9 1098.81  4800.2 1096.29  4809.8 1096.27  4815.3 1094.90
  4844.3 1091.41  4861.2 1089.68  4866.7 1090.15  4877.4 1088.95  4884.1 1087.23
  4935.4 1082.73  4975.8 1076.86  4981.3 1073.46  4987.6 1071.76  5000.0 1070.76
  5006.3 1069.19  5006.6 1068.69  5010.3 1069.19  5029.0 1073.42  5039.1 1076.49
  5049.2 1077.97  5079.1 1077.79  5149.9 1080.36  5180.5 1082.65  5220.7 1083.89
  5241.1 1086.25  5271.4 1086.81  5321.9 1090.29  5352.2 1093.43  5402.8 1097.21
#Mann=3,-1,0
  4778.2    0.12       0  5006.3    0.07       0  5010.3    0.12       0
Bank Sta=5006.3,5010.3
Exp/Cntr=0.3,0.1

Type RM Length L Ch R = 1,15019,467,467,467
BEGIN DESCRIPTION:
Mapping XS 1cffd4b3
END DESCRIPTION:
XS GIS Cut Line= 2
      2898503.41     10154316.33      2899230.30     10154146.36
#Sta/Elev= 30
  4586.7 1083.22  4629.6 1082.52  4708.9 1081.07  4714.0 1081.82  4751.4 1079.65
  4756.5 1080.36  4793.9 1078.85  4799.0 1079.84  4804.7 1078.84  4841.5 1076.63
  4866.3 1076.38  4926.5 1072.17  4931.6 1072.59  4969.0 1070.56  4974.1 1070.15
  4979.3 1067.67  4999.8 1065.62  5008.1 1063.62  5008.3 1063.12  5012.1 1063.62
  5016.6 1065.39  5021.8 1065.21  5030.6 1070.05  5059.1 1071.69  5071.7 1073.23
  5092.3 1073.13  5112.8 1074.69  5215.5 1078.86  5307.9 1081.20  5333.2 1082.58
#Mann=4,-1,0
  4586.7    0.05       0  4629.6    0.12       0  5008.1    0.07       0
  5012.1    0.12       0
Bank Sta=5008.1,5012.1
Exp/Cntr=0.3,0.1

Type RM Length L Ch R = 1,14552,552,552,552
BEGIN DESCRIPTION:
Mapping XS ccd40121
END DESCRIPTION:
XS GIS Cut Line= 2
      2898611.84     10154591.18      2899378.61     10154583.95
#Sta/Elev= 30
  4601.2 1072.89  4665.0 1071.05  4745.1 1070.18  4765.1 1068.62  4775.1 1068.75
  4785.1 1068.08  4835.1 1068.31  4855.1 1067.52  4875.1 1067.91  4885.1 1066.69
  4895.1 1066.50  4915.1 1064.85  4928.5 1065.33  4955.1 1063.67  4975.1 1063.37
  4995.1 1060.94  5013.1 1059.93  5013.3 1059.43  5016.8 1059.43  5017.1 1059.93
  5035.1 1060.66  5045.1 1062.06  5075.1 1063.06  5087.7 1064.22  5105.1 1065.35
  5195.1 1069.08  5245.1 1069.77  5305.1 1071.57  5355.1 1074.23  5368.0 1073.69
#Mann=4,-1,0
  4601.2    0.05       0  5013.1    0.03       0  5017.1    0.05       0
  5087.7    0.12       0
Bank Sta=5013.1,5017.1
Exp/Cntr=0.3,0.1

Type RM Length L Ch R = 1,14000,500,500,500
BEGIN DESCRIPTION:
DRY BRANCH 28.0
END DESCRIPTION:
XS GIS Cut Line= 3
      2898855.68     10155053.11      2899181.24     10155079.21
      2899455.67     10154753.13
#Sta/Elev= 30
  4673.4 1070.58  4752.0 1066.65  4803.8 1064.37  4823.9 1062.78  4854.0 1061.62
  4860.0 1060.84  4865.1 1061.02  4914.2 1057.86  4924.2 1057.75  4964.3 1054.30
  4982.8 1051.93  4987.8 1052.00  4999.7 1049.79  5006.0 1049.71  5006.2 1049.21
  5009.7 1049.21  5010.0 1049.71  5014.6 1050.81  5028.9 1052.64  5035.4 1052.38
  5057.5 1055.10  5156.4 1060.40  5185.0 1063.00  5191.5 1062.48  5248.7 1065.19
  5277.3 1065.84  5334.5 1068.78  5355.3 1069.28  5361.9 1070.05  5426.2 1072.47
#Mann=5,-1,0
  4673.4    0.05       0  4752.0    0.12       0  5006.0    0.07       0
  5010.0    0.12       0  5361.9    0.05       0
Bank Sta=5006,5010
Exp/Cntr=0.3,0.1

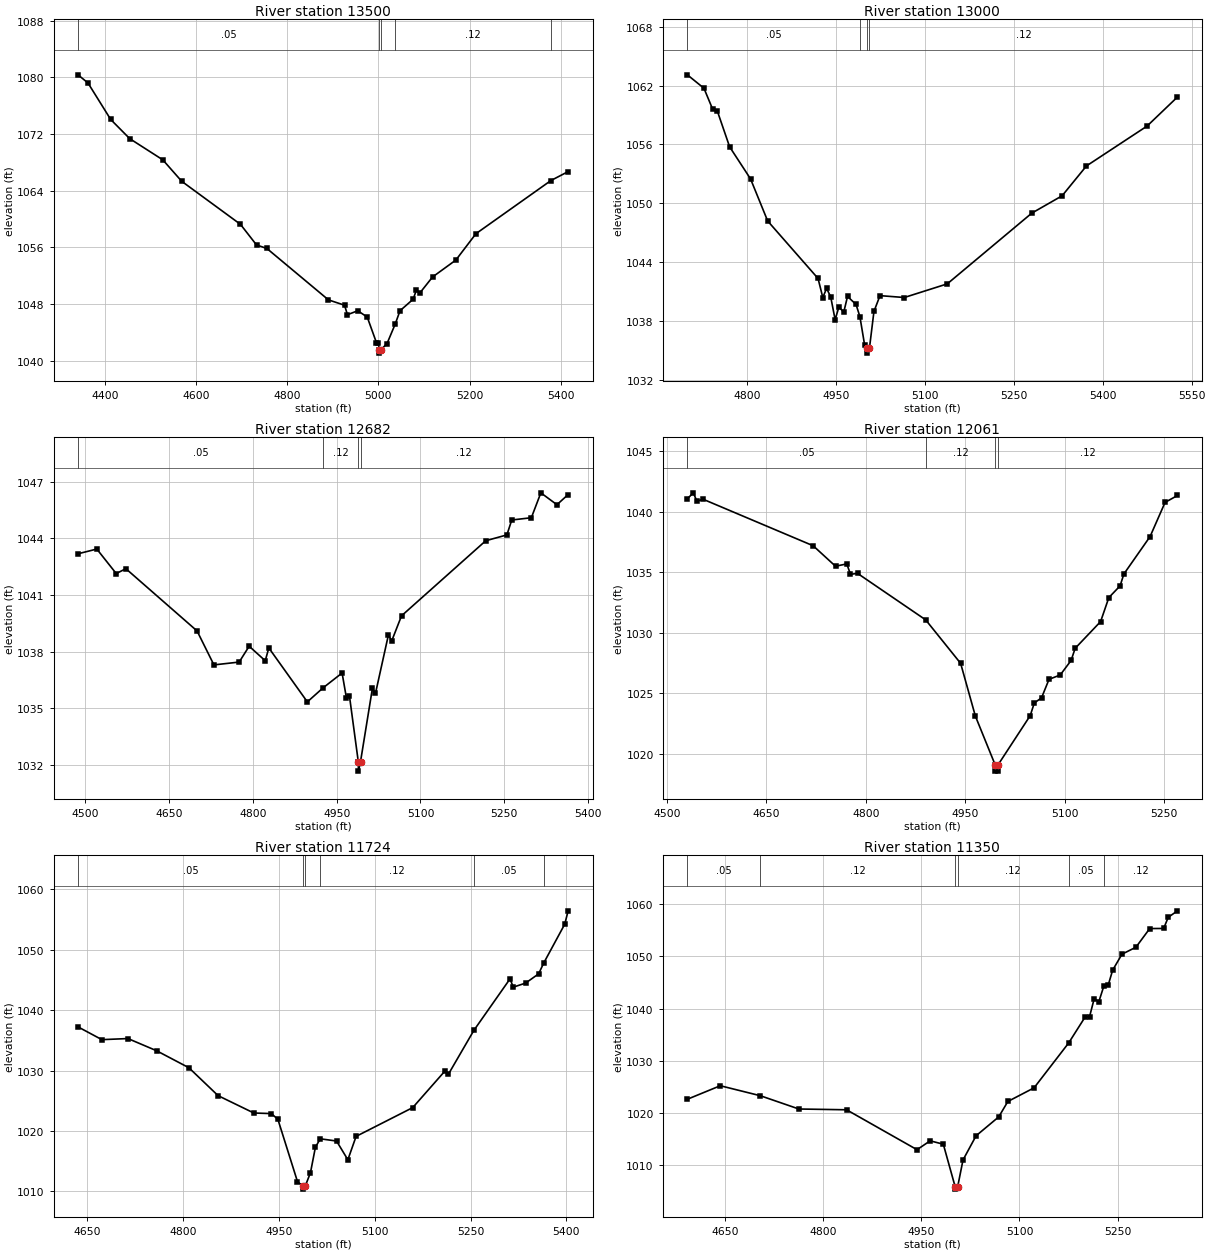
Type RM Length L Ch R = 1,13500,500,500,500
BEGIN DESCRIPTION:
DRY BRANCH 27.0
END DESCRIPTION:
XS GIS Cut Line= 3
      2898905.65     10155903.14      2899429.71     10155502.92
      2899655.71     10155153.07
#Sta/Elev= 30
  4340.6 1080.35  4362.4 1079.20  4412.3 1074.05  4454.0 1071.35  4526.6 1068.36
  4568.2 1065.33  4697.1 1059.26  4732.4 1056.35  4755.2 1055.85  4890.3 1048.60
  4925.6 1047.85  4932.0 1046.51  4954.7 1047.07  4975.5 1046.17  4995.7 1042.56
  5000.0 1042.56  5001.8 1041.59  5002.0 1041.09  5005.8 1041.59  5018.9 1042.44
  5036.8 1045.18  5047.4 1047.07  5076.3 1048.70  5083.1 1049.95  5091.5 1049.62
  5118.8 1051.83  5170.0 1054.22  5214.1 1057.94  5378.5 1065.43  5416.5 1066.70
#Mann=5,-1,0
  4340.6    0.05       0  5001.8    0.05       0  5005.8    0.05       0
  5036.8    0.12       0  5378.5    0.05       0
Bank Sta=5001.8,5005.8
Exp/Cntr=0.3,0.1

Type RM Length L Ch R = 1,13000,318,318,318
BEGIN DESCRIPTION:
DRY BRANCH 26.0
END DESCRIPTION:
XS GIS Cut Line= 3
      2899455.70     10156053.09      2899641.80     10155816.77
      2899755.68     10155303.14
#Sta/Elev= 30
  4699.2 1063.09  4727.2 1061.72  4741.7 1059.61  4749.7 1059.41  4770.5 1055.75
  4805.8 1052.48  4834.7 1048.19  4919.7 1042.33  4927.7 1040.39  4934.1 1041.31
  4941.0 1040.47  4948.5 1038.13  4954.9 1039.43  4963.0 1038.88  4969.4 1040.50
  4983.8 1039.68  4990.3 1038.44  4998.2 1035.57  5002.4 1035.22  5002.7 1034.72
  5006.4 1035.22  5014.0 1038.97  5024.2 1040.58  5065.2 1040.39  5137.7 1041.78
  5280.3 1048.99  5331.5 1050.76  5372.5 1053.80  5474.9 1057.87  5526.1 1060.83
#Mann=4,-1,0
  4699.2    0.05       0  4990.3    0.12       0  5002.4    0.07       0
  5006.4    0.12       0
Bank Sta=5002.4,5006.4
Exp/Cntr=0.3,0.1

Type RM Length L Ch R = 1,12682,621,621,621
BEGIN DESCRIPTION:
Mapping XS a2a2e7e4
END DESCRIPTION:
XS GIS Cut Line= 2
      2899725.73     10156265.65      2900080.15     10155462.79
#Sta/Elev= 30
  4486.8 1043.18  4520.4 1043.43  4555.2 1042.13  4572.4 1042.39  4699.9 1039.09
  4730.1 1037.29  4775.3 1037.44  4793.2 1038.28  4822.0 1037.51  4828.4 1038.19
  4897.4 1035.33  4925.4 1036.07  4959.6 1036.86  4967.3 1035.55  4972.8 1035.64
  4988.6 1032.16  4988.9 1031.66  4992.6 1032.16  5013.9 1036.05  5019.4 1035.78
  5042.7 1038.90  5048.2 1038.54  5066.0 1039.89  5216.8 1043.87  5254.7 1044.18
  5263.4 1044.97  5298.5 1045.09  5315.5 1046.41  5344.3 1045.78  5364.4 1046.32
#Mann=4,-1,0
  4486.8    0.05       0  4925.4    0.12       0  4988.6    0.07       0
  4992.6    0.12       0
Bank Sta=4988.6,4992.6
Exp/Cntr=0.3,0.1

Type RM Length L Ch R = 1,12061,337,337,337
BEGIN DESCRIPTION:
Mapping XS a0cc93a3
END DESCRIPTION:
XS GIS Cut Line= 2
      2899924.69     10156403.02      2900590.05     10156081.19
#Sta/Elev= 30
  4531.0 1041.07  4540.0 1041.56  4545.5 1040.85  4554.3 1041.04  4720.7 1037.19
  4754.4 1035.50  4771.4 1035.69  4777.0 1034.83  4787.6 1034.91  4890.4 1031.07
  4943.1 1027.48  4965.3 1023.13  4995.3 1019.08  4995.6 1018.58  4999.1 1018.58
  4999.3 1019.08  5048.1 1023.17  5054.2 1024.21  5065.1 1024.63  5076.4 1026.16
  5093.3 1026.52  5109.7 1027.72  5115.8 1028.72  5154.2 1030.93  5166.6 1032.91
  5183.6 1033.88  5189.2 1034.85  5228.8 1037.95  5251.4 1040.77  5270.1 1041.34
#Mann=4,-1,0
  4531.0    0.05       0  4890.4    0.12       0  4995.3    0.07       0
  4999.3    0.12       0
Bank Sta=4995.3,4999.3
Exp/Cntr=0.3,0.1

Type RM Length L Ch R = 1,11724,374,374,374
BEGIN DESCRIPTION:
Mapping XS 1133c203
END DESCRIPTION:
XS GIS Cut Line= 2
      2900109.09     10156562.16      2900861.01     10156410.33
#Sta/Elev= 30
  4635.6 1037.22  4672.9 1035.11  4713.7 1035.29  4758.4 1033.28  4809.1 1030.46
  4854.8 1025.84  4910.7 1022.97  4938.2 1022.87  4948.4 1021.92  4979.0 1011.63
  4987.2 1010.87  4987.4 1010.37  4991.2 1010.87  4999.4 1013.10  5007.1 1017.30
  5014.7 1018.70  5040.2 1018.33  5057.9 1015.23  5070.8 1019.10  5159.4 1023.86
  5210.2 1029.96  5215.3 1029.39  5255.1 1036.64  5311.7 1045.17  5316.8 1043.80
  5336.1 1044.47  5356.5 1046.00  5364.4 1047.78  5397.3 1054.21  5402.7 1056.43
#Mann=6,-1,0
  4635.6    0.05       0  4987.2    0.03       0  4991.2    0.05       0
  5014.7    0.12       0  5255.1    0.05       0  5364.4    0.12       0
Bank Sta=4987.2,4991.2
Exp/Cntr=0.3,0.1

Type RM Length L Ch R = 1,11350,350,350,350
BEGIN DESCRIPTION:
Mapping XS a38a0449
END DESCRIPTION:
XS GIS Cut Line= 4
      2900275.43     10156779.15      2900514.14     10156768.30
      2900767.29     10156746.60      2900950.00     10156567.48
#Sta/Elev= 30
  4592.5 1022.62  4642.8 1025.21  4703.9 1023.30  4762.9 1020.75  4835.8 1020.60
  4943.4 1012.95  4963.5 1014.65  4983.6 1014.00  5001.6 1005.89  5001.9 1005.39
  5005.6 1005.89  5013.7 1010.98  5033.7 1015.62  5068.3 1019.24  5082.2 1022.19
  5122.3 1024.81  5175.2 1033.42  5200.0 1038.33  5207.1 1038.46  5214.1 1041.88
  5221.3 1041.34  5228.8 1044.28  5235.4 1044.44  5242.4 1047.38  5256.6 1050.43
  5277.9 1051.76  5299.0 1055.34  5320.3 1055.36  5327.3 1057.50  5341.4 1058.74
#Mann=6,-1,0
  4592.5    0.05       0  4703.9    0.12       0  5001.6    0.07       0
  5005.6    0.12       0  5175.2    0.05       0  5228.8    0.12       0
Bank Sta=5001.6,5005.6
Exp/Cntr=0.3,0.1

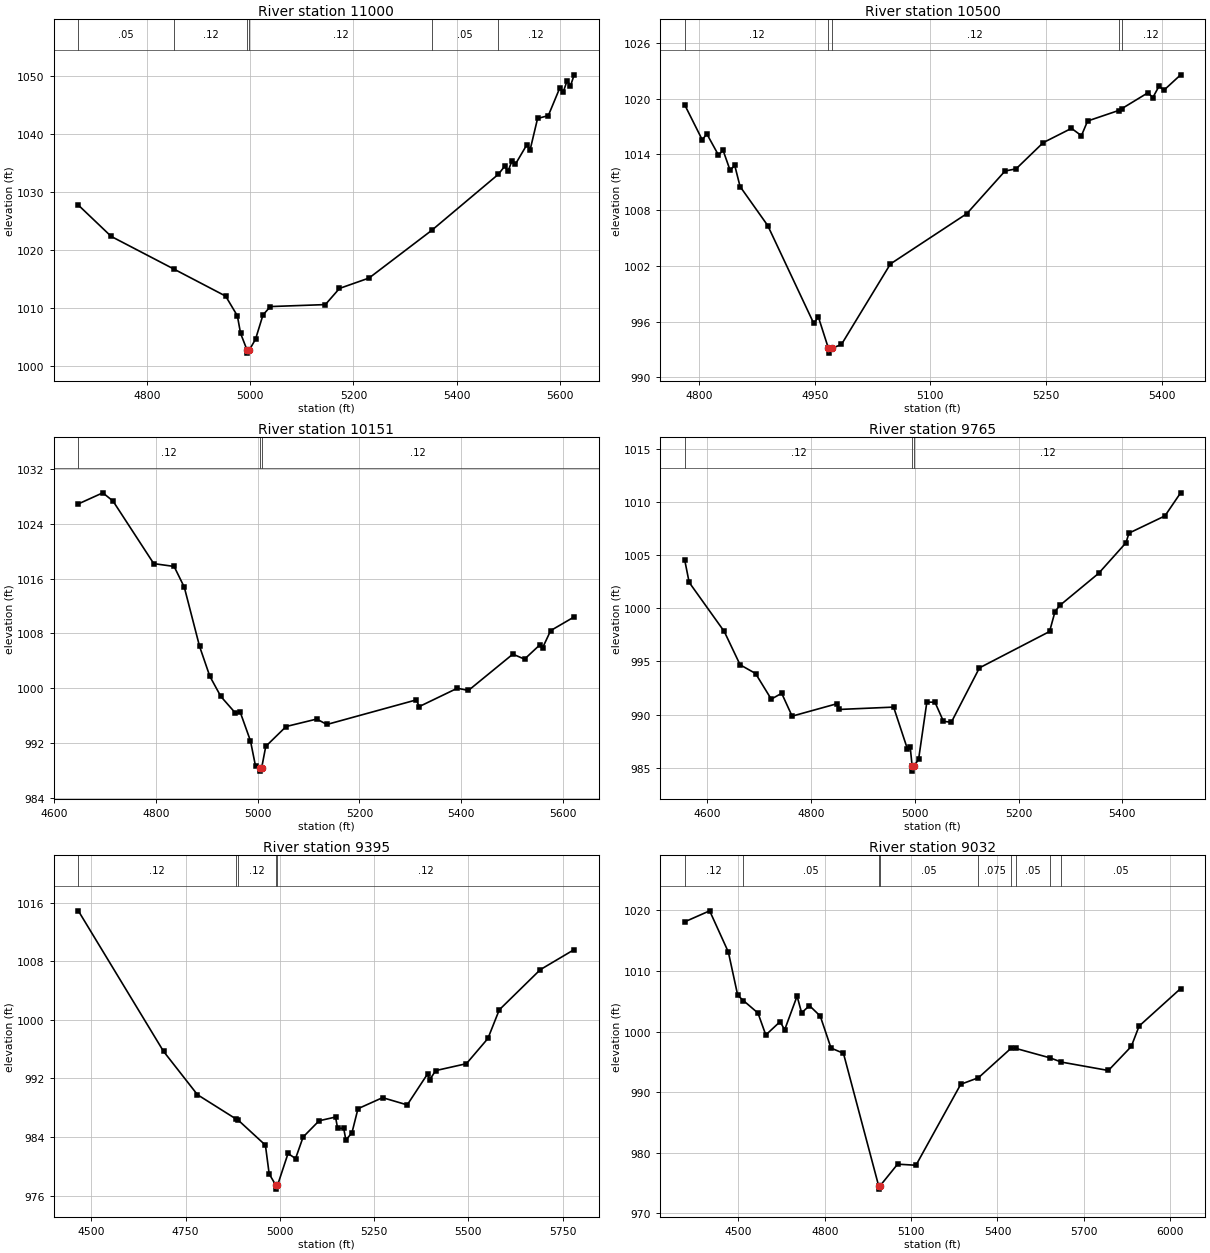
Type RM Length L Ch R = 1,11000,500,500,500
BEGIN DESCRIPTION:
DRY BRANCH 22.0
END DESCRIPTION:
XS GIS Cut Line= 3
      2900455.66     10157353.14      2900653.07     10157084.72
      2901055.67     10156603.13
#Sta/Elev= 30
  4666.8 1027.74  4730.5 1022.35  4852.7 1016.70  4952.3 1012.08  4975.0 1008.69
  4981.2 1005.68  4993.9 1002.77  4994.1 1002.27  4997.9 1002.77  5010.2 1004.66
  5024.6 1008.83  5038.9 1010.28  5145.5 1010.62  5172.9 1013.40  5230.2 1015.19
  5351.6 1023.39  5480.7 1033.03  5493.0 1034.41  5499.6 1033.58  5507.3 1035.37
  5513.9 1034.78  5536.0 1038.12  5542.5 1037.30  5556.8 1042.64  5577.6 1043.13
  5599.7 1047.86  5606.3 1047.14  5614.1 1049.15  5620.6 1048.24  5627.7 1050.15
#Mann=6,-1,0
  4666.8    0.05       0  4852.7    0.12       0  4993.9    0.07       0
  4997.9    0.12       0  5351.6    0.05       0  5480.7    0.12       0
Bank Sta=4993.9,4997.9
Exp/Cntr=0.3,0.1

Type RM Length L Ch R = 1,10500,349,349,349
BEGIN DESCRIPTION:
DRY BRANCH 21.0
END DESCRIPTION:
XS GIS Cut Line= 3
      2900755.70     10157603.10      2900938.46     10157483.17
      2901205.70     10157153.09
#Sta/Elev= 30
  4781.4 1019.32  4804.0 1015.58  4810.0 1016.21  4825.1 1013.93  4831.1 1014.44
  4840.2 1012.29  4846.2 1012.82  4853.1 1010.55  4889.0 1006.35  4948.7  995.82
  4954.7  996.51  4967.8  993.12  4968.0  992.62  4971.8  993.12  4984.7  993.56
  5048.2 1002.22  5147.3 1007.63  5196.9 1012.22  5211.2 1012.45  5246.4 1015.27
  5283.1 1016.81  5296.0 1016.02  5304.0 1017.60  5344.2 1018.73  5348.4 1018.93
  5382.3 1020.64  5388.7 1020.13  5396.7 1021.35  5403.1 1020.92  5424.7 1022.57
#Mann=5,-1,0
  4781.4    0.12       0  4967.8    0.07       0  4971.8    0.12       0
  5344.2    0.05       0  5348.4    0.12       0
Bank Sta=4967.8,4971.8
Exp/Cntr=0.3,0.1

Type RM Length L Ch R = 1,10151,386,386,386
BEGIN DESCRIPTION:
Mapping XS 908e1fd2
END DESCRIPTION:
XS GIS Cut Line= 3
      2900557.57     10157798.99      2901215.74     10157820.69
      2901490.57     10157665.19
#Sta/Elev= 30
  4647.7 1026.92  4695.8 1028.54  4715.8 1027.34  4795.9 1018.19  4835.9 1017.78
  4855.9 1014.75  4885.9 1006.10  4906.0 1001.74  4927.7  998.78  4956.0  996.38
  4966.0  996.44  4986.0  992.27  4996.0  988.54  5004.0  988.36  5004.3  987.86
  5008.0  988.36  5016.0  991.48  5056.0  994.38  5116.1  995.47  5136.1  994.68
  5311.7  998.27  5317.7  997.30  5392.5  999.98  5414.2  999.65  5501.5 1004.96
  5524.5 1004.23  5554.2 1006.29  5559.9 1005.87  5575.8 1008.40  5622.0 1010.40
#Mann=3,-1,0
  4647.7    0.12       0  5004.0    0.07       0  5008.0    0.12       0
Bank Sta=5004,5008
Exp/Cntr=0.3,0.1

Type RM Length L Ch R = 1,9765,370,370,370
BEGIN DESCRIPTION:
Mapping XS 3711aadd
END DESCRIPTION:
XS GIS Cut Line= 3
      2900540.10     10158097.46      2900935.93     10158139.13
      2901465.87     10157967.68
#Sta/Elev= 30
  4557.1 1004.49  4565.5 1002.43  4633.1  997.81  4663.6  994.68  4693.4  993.86
  4723.6  991.45  4743.7  992.00  4763.8  989.85  4849.6  991.01  4854.6  990.48
  4959.3  990.70  4986.0  986.75  4991.3  986.92  4994.9  985.18  4995.1  984.68
  4998.9  985.18  5007.4  985.79  5023.3  991.17  5038.9  991.16  5055.3  989.36
  5070.5  989.28  5124.6  994.39  5259.7  997.81  5270.2  999.69  5279.4 1000.26
  5354.2 1003.28  5406.8 1006.15  5412.6 1007.06  5481.9 1008.68  5512.1 1010.85
#Mann=3,-1,0
  4557.1    0.12       0  4994.9    0.07       0  4998.9    0.12       0
Bank Sta=4994.9,4998.9
Exp/Cntr=0.3,0.1

Type RM Length L Ch R = 1,9395,363,363,363
BEGIN DESCRIPTION:
Mapping XS de80152d
END DESCRIPTION:
XS GIS Cut Line= 3
      2900289.93     10158424.64      2900893.87     10158446.34
      2901515.87     10158102.79
#Sta/Elev= 30
  4465.6 1014.91  4691.5  995.71  4781.6  989.78  4883.4  986.48  4889.1  986.33
  4961.7  982.89  4971.7  978.96  4989.7  977.38  4989.9  976.88  4993.7  977.38
  5021.7  981.75  5041.7  981.06  5061.7  984.00  5104.1  986.22  5147.6  986.73
  5153.3  985.19  5169.4  985.18  5175.1  983.60  5191.2  984.58  5207.2  987.87
  5272.5  989.38  5337.8  988.39  5391.7  992.62  5397.4  991.83  5413.4  993.08
  5494.7  994.02  5551.8  997.47  5581.9 1001.38  5690.7 1006.87  5780.5 1009.61
#Mann=5,-1,0
  4465.6    0.12       0  4883.4    0.05       0  4889.1    0.12       0
  4989.7    0.07       0  4993.7    0.12       0
Bank Sta=4989.7,4993.7
Exp/Cntr=0.3,0.1

Type RM Length L Ch R = 1,9032,151,151,151
BEGIN DESCRIPTION:
Mapping XS de061b54
END DESCRIPTION:
XS GIS Cut Line= 5
      2900145.29     10159082.83      2900423.73     10158996.04
      2900738.36     10158815.22      2901045.76     10158518.67
      2901588.27     10158178.70
#Sta/Elev= 30
  4314.1 1018.13  4400.4 1019.94  4465.4 1013.13  4497.9 1005.99  4517.3 1005.14
  4568.2 1003.07  4595.4  999.45  4645.1 1001.65  4660.9 1000.30  4704.0 1005.86
  4719.8 1003.11  4747.1 1004.29  4784.5 1002.57  4821.9  997.29  4865.0  996.43
  4987.5  974.51  4987.8  974.01  4991.5  974.51  5053.1  978.13  5116.9  977.95
  5272.3  991.31  5334.0  992.40  5448.3  997.31  5463.8  997.23  5583.5  995.66
  5621.6  994.98  5785.1  993.59  5864.7  997.56  5891.8 1000.92  6036.0 1007.11
#Mann=9,-1,0
  4314.1    0.12       0  4517.3    0.05       0  4987.5    0.03       0
  4991.5    0.05       0  5334.0   0.075       0  5448.3    0.12       0
  5463.8    0.05       0  5583.5   0.075       0  5621.6    0.05       0
Bank Sta=4987.5,4991.5
Exp/Cntr=0.3,0.1

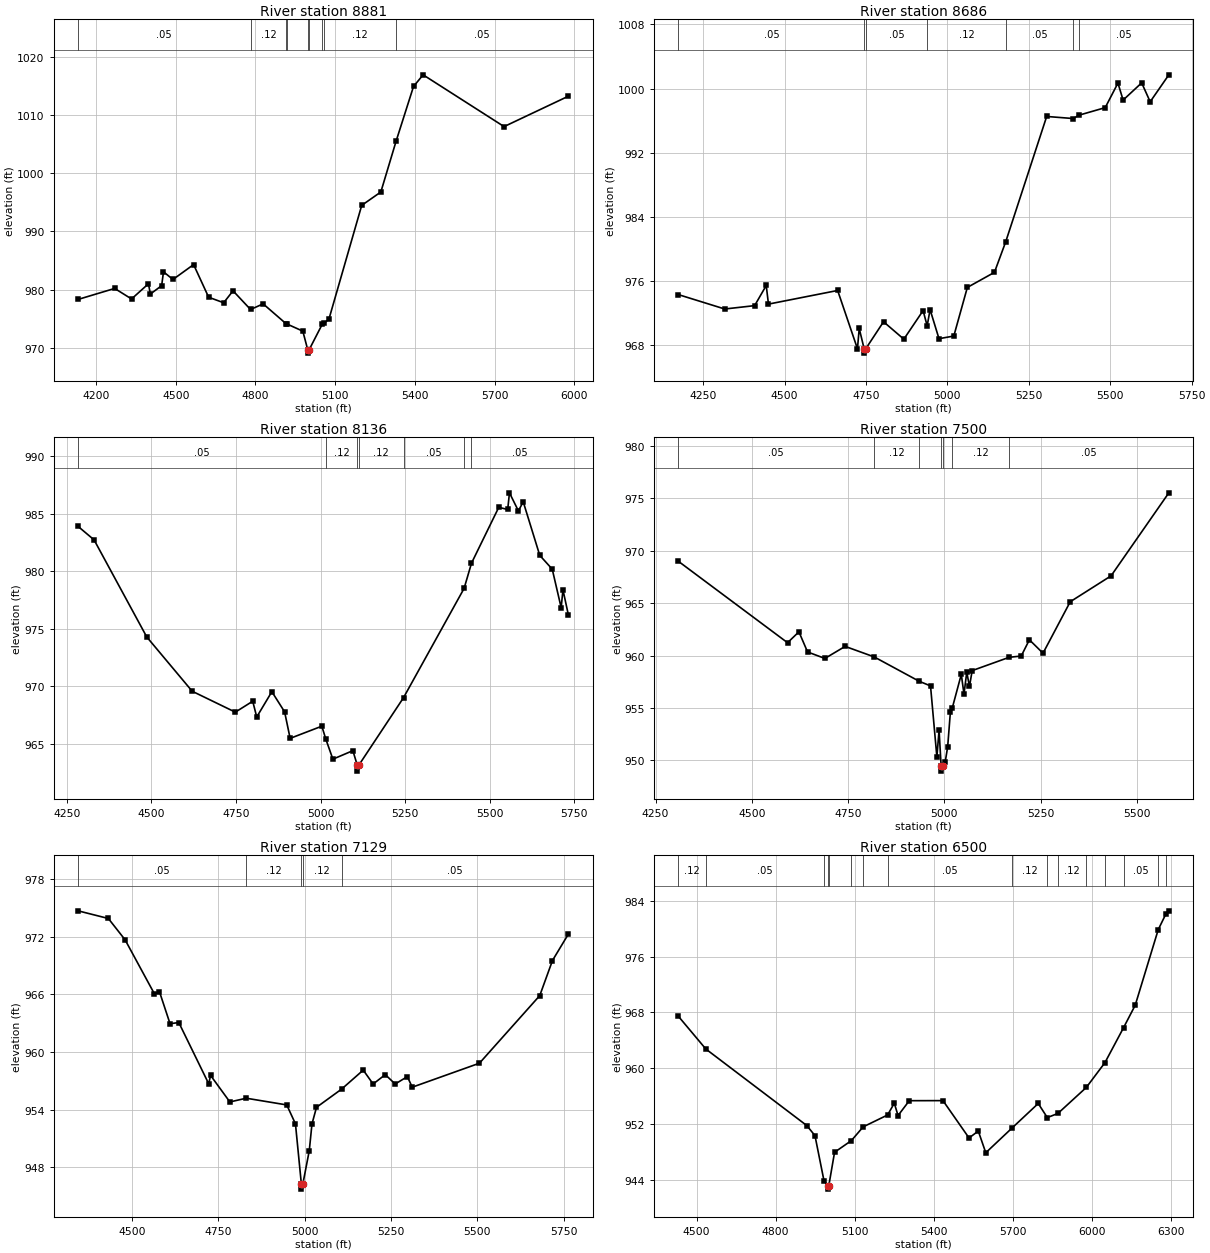
Type RM Length L Ch R = 1,8881,195,195,195
BEGIN DESCRIPTION:
Mapping XS c06824fb
END DESCRIPTION:
XS GIS Cut Line= 6
      2900213.96     10159505.98      2900510.52     10159227.49
      2900680.50     10159061.14      2900904.72     10158869.46
      2901378.48     10158551.22      2901675.02     10158395.71
#Sta/Elev= 30
  4132.3  978.32  4270.1  980.21  4333.6  978.40  4397.1  981.01  4404.5  979.25
  4446.9  980.69  4453.8  983.07  4489.4  981.75  4567.1  984.31  4623.7  978.70
  4680.2  977.75  4715.5  979.80  4781.4  976.59  4828.8  977.56  4916.2  974.10
  4918.2  974.10  4978.1  972.87  4997.0  969.59  4997.2  969.09  5001.0  969.59
  5051.0  974.04  5058.9  974.22  5076.7  974.99  5199.7  994.49  5271.7  996.79
  5329.0 1005.51  5394.7 1014.93  5430.8 1016.93  5735.5 1008.03  5977.5 1013.26
#Mann=9,-1,0
  4132.3    0.05       0  4781.4    0.12       0  4916.2    0.05       0
  4918.2    0.12       0  4997.0    0.07       0  5001.0    0.12       0
  5051.0    0.05       0  5058.9    0.12       0  5329.0    0.05       0
Bank Sta=4997,5001
Exp/Cntr=0.3,0.1

Type RM Length L Ch R = 1,8686,550,550,550
BEGIN DESCRIPTION:
Mapping XS e3d1143c
END DESCRIPTION:
XS GIS Cut Line= 4
      2900264.07     10159592.24      2900602.60     10159232.88
      2900847.39     10159118.30      2901560.76     10158915.22
#Sta/Elev= 30
  4174.2  974.32  4316.2  972.53  4408.0  972.95  4443.6  975.46  4450.5  973.14
  4662.9  974.84  4723.7  967.58  4729.2  970.10  4744.5  967.53  4744.7  967.03
  4748.5  967.53  4803.8  970.94  4866.2  968.77  4925.3  972.33  4937.8  970.44
  4946.8  972.45  4974.1  968.83  5019.6  969.16  5061.2  975.22  5144.4  977.10
  5179.0  980.91  5304.8  996.53  5386.8  996.27  5403.2  996.68  5484.5  997.63
  5523.6 1000.69  5539.5  998.57  5596.5 1000.72  5622.6  998.36  5679.9 1001.72
#Mann=7,-1,0
  4174.2    0.05       0  4744.5    0.07       0  4748.5    0.05       0
  4937.8    0.12       0  5179.0    0.05       0  5386.8    0.12       0
  5403.2    0.05       0
Bank Sta=4744.5,4748.5
Exp/Cntr=0.3,0.1

Type RM Length L Ch R = 1,8136,636,636,636
BEGIN DESCRIPTION:
Mapping XS cbfd2322
END DESCRIPTION:
XS GIS Cut Line= 4
      2900144.29     10159878.69      2900508.85     10159540.17
      2900784.89     10159394.34      2901392.44     10159191.82
#Sta/Elev= 30
  4282.9  983.89  4330.2  982.72  4486.1  974.27  4620.4  969.55  4748.0  967.73
  4799.4  968.68  4811.3  967.31  4856.0  969.51  4893.7  967.76  4910.1  965.45
  5003.8  966.51  5015.3  965.41  5036.5  963.64  5095.6  964.38  5108.8  963.10
  5109.0  962.60  5112.8  963.10  5245.4  968.99  5424.6  978.50  5446.4  980.69
  5527.1  985.55  5553.5  985.36  5558.7  986.81  5585.1  985.24  5599.4  986.03
  5648.3  981.37  5685.2  980.17  5711.6  976.82  5716.9  978.37  5733.0  976.18
#Mann=7,-1,0
  4282.9    0.05       0  5015.3    0.12       0  5108.8    0.03       0
  5112.8    0.12       0  5245.4    0.05       0  5424.6    0.12       0
  5446.4    0.05       0
Bank Sta=5108.8,5112.8
Exp/Cntr=0.3,0.1

Type RM Length L Ch R = 1,7500,371,371,371
BEGIN DESCRIPTION:
DRY BRANCH 15.0
END DESCRIPTION:
XS GIS Cut Line= 3
      2900517.74     10160117.15      2901131.50     10159801.00
      2901548.47     10159393.83
#Sta/Elev= 30
  4309.6  968.99  4592.8  961.23  4622.3  962.27  4644.7  960.35  4689.7  959.73
  4742.3  960.88  4817.5  959.88  4934.7  957.55  4964.0  957.11  4980.5  950.33
  4986.2  952.90  4991.5  949.48  4991.7  948.98  4995.5  949.48  5002.1  949.85
  5008.5  951.29  5015.6  954.63  5020.7  955.03  5043.9  958.21  5050.9  956.33
  5058.1  958.42  5065.1  957.06  5072.2  958.57  5168.3  959.84  5199.5  959.96
  5220.7  961.51  5256.1  960.23  5326.8  965.14  5432.8  967.61  5582.8  975.53
#Mann=7,-1,0
  4309.6    0.05       0  4817.5    0.12       0  4934.7    0.05       0
  4991.5    0.05       0  4995.5    0.05       0  5020.7    0.12       0
  5168.3    0.05       0
Bank Sta=4991.5,4995.5
Exp/Cntr=0.3,0.1

Type RM Length L Ch R = 1,7129,629,629,629
BEGIN DESCRIPTION:
Mapping XS c5af9aaf
END DESCRIPTION:
XS GIS Cut Line= 4
      2900687.70     10160337.76      2901277.22     10160124.38
      2901606.31     10159849.53      2901794.38     10159538.49
#Sta/Elev= 30
  4344.2  974.72  4431.9  973.92  4480.3  971.70  4565.4  966.05  4579.8  966.29
  4610.4  962.95  4635.8  963.07  4722.4  956.68  4727.7  957.56  4783.6  954.79
  4831.0  955.18  4948.2  954.48  4973.4  952.51  4990.6  946.20  4990.9  945.70
  4994.6  946.20  5013.4  949.71  5021.2  952.49  5034.3  954.23  5107.0  956.13
  5169.6  958.11  5198.2  956.66  5233.4  957.64  5262.0  956.66  5297.2  957.43
  5311.5  956.33  5505.9  958.83  5680.5  965.88  5717.3  969.54  5763.4  972.30
#Mann=5,-1,0
  4344.2    0.05       0  4831.0    0.12       0  4990.6    0.07       0
  4994.6    0.12       0  5107.0    0.05       0
Bank Sta=4990.6,4994.6
Exp/Cntr=0.3,0.1

Type RM Length L Ch R = 1,6500,500,500,500
BEGIN DESCRIPTION:
DRY BRANCH 13.0
END DESCRIPTION:
XS GIS Cut Line= 3
      2900905.67     10160853.12      2901440.98     10160661.99
      2902405.65     10159803.14
#Sta/Elev= 30
  4431.6  967.43  4535.4  962.76  4918.5  951.79  4949.3  950.35  4983.4  943.91
  4997.8  943.19  4998.1  942.69  5001.8  943.19  5023.6  947.97  5087.3  949.64
  5132.1  951.61  5224.7  953.31  5250.2  955.00  5264.4  953.23  5307.1  955.36
  5434.8  955.37  5533.7  950.02  5568.8  951.01  5597.2  947.90  5696.4  951.43
  5796.2  954.96  5830.6  952.94  5870.7  953.53  5978.6  957.26  6049.2  960.81
  6119.7  965.81  6164.1  969.04  6251.5  979.88  6280.8  982.14  6291.6  982.56
#Mann=16,-1,0
  4431.6    0.12       0  4535.4    0.05       0  4983.4    0.12       0
  4997.8    0.07       0  5001.8    0.12       0  5087.3    0.05       0
  5132.1    0.12       0  5224.7    0.05       0  5696.4    0.12       0
  5830.6    0.05       0  5870.7    0.12       0  5978.6    0.05       0
  6049.2    0.12       0  6119.7    0.05       0  6251.5    0.12       0
  6280.8    0.05       0
Bank Sta=4997.8,5001.8
Exp/Cntr=0.3,0.1

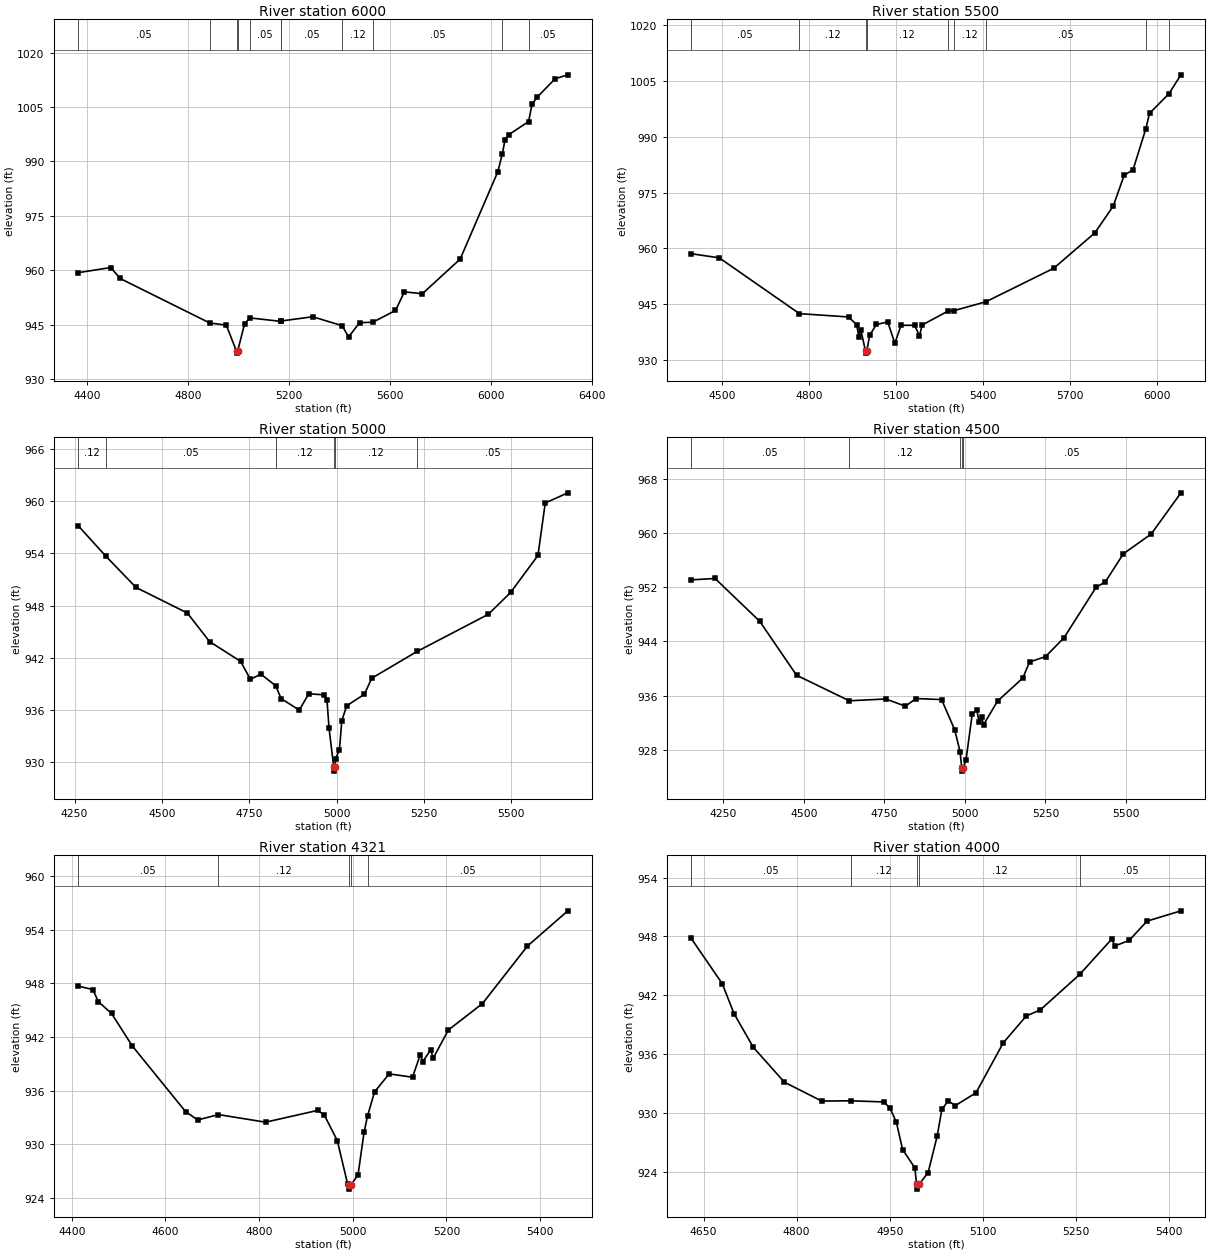
Type RM Length L Ch R = 1,6000,500,500,500
BEGIN DESCRIPTION:
DRY BRANCH 12.0
END DESCRIPTION:
XS GIS Cut Line= 3
      2901349.23     10161155.73      2901890.72     10160821.94
      2902705.70     10159803.09
#Sta/Elev= 30
  4363.9  959.30  4493.8  960.73  4530.5  957.71  4885.9  945.42  4951.5  944.82
  4992.1  937.60  4992.4  937.10  4996.1  937.60  5024.1  945.23  5044.9  946.82
  5166.7  945.87  5168.7  945.97  5293.8  947.14  5410.1  944.68  5436.2  941.58
  5479.5  945.51  5531.8  945.63  5621.9  948.87  5657.2  954.01  5728.4  953.50
  5878.1  963.05  6026.9  987.08  6045.6  992.17  6055.8  995.96  6070.2  997.37
  6149.4 1001.03  6163.0 1005.82  6183.8 1007.79  6254.3 1012.83  6304.7 1013.92
#Mann=11,-1,0
  4363.9    0.05       0  4885.9    0.12       0  4992.1    0.07       0
  4996.1    0.12       0  5044.9    0.05       0  5166.7    0.12       0
  5168.7    0.05       0  5410.1    0.12       0  5531.8    0.05       0
  6045.6    0.12       0  6149.4    0.05       0
Bank Sta=4992.1,4996.1
Exp/Cntr=0.3,0.1

Type RM Length L Ch R = 1,5500,500,500,500
BEGIN DESCRIPTION:
DRY BRANCH 11.0
END DESCRIPTION:
XS GIS Cut Line= 3
      2901874.63     10161359.01      2902296.38     10160923.44
      2902655.67     10159903.15
#Sta/Elev= 30
  4393.7  958.58  4490.5  957.48  4766.9  942.51  4936.1  941.62  4964.4  939.52
  4971.5  936.29  4978.5  938.15  4994.7  932.42  4995.0  931.92  4998.7  932.42
  5009.3  936.76  5032.2  939.60  5071.2  940.29  5095.8  934.55  5117.0  939.38
  5164.1  939.39  5180.6  936.52  5189.7  939.46  5278.0  943.15  5300.8  943.34
  5409.7  945.70  5643.5  954.69  5784.9  964.16  5848.5  971.36  5885.8  979.57
  5916.8  981.14  5960.4  992.00  5973.4  996.22  6040.2 1001.48  6081.7 1006.56
#Mann=9,-1,0
  4393.7    0.05       0  4766.9    0.12       0  4994.7    0.07       0
  4998.7    0.12       0  5278.0    0.05       0  5300.8    0.12       0
  5409.7    0.05       0  5960.4    0.12       0  6040.2    0.05       0
Bank Sta=4994.7,4998.7
Exp/Cntr=0.3,0.1

Type RM Length L Ch R = 1,5000,500,500,500
BEGIN DESCRIPTION:
DRY BRANCH 10.0
END DESCRIPTION:
XS GIS Cut Line= 3
      2902005.70     10161403.10      2902635.58     10161014.71
      2903055.70     10160503.10
#Sta/Elev= 30
  4260.0  957.21  4340.2  953.66  4426.1  950.08  4572.8  947.14  4636.7  943.84
  4725.4  941.57  4753.4  939.50  4783.4  940.10  4826.1  938.75  4841.3  937.28
  4893.4  935.96  4920.5  937.84  4964.9  937.71  4972.6  937.16  4978.5  933.88
  4991.9  929.43  4992.1  928.93  4995.9  929.43  4997.1  930.35  5008.3  931.38
  5015.0  934.73  5029.1  936.46  5079.7  937.78  5100.8  939.63  5230.9  942.72
  5434.5  946.99  5498.4  949.51  5576.6  953.77  5597.4  959.81  5662.0  960.98
#Mann=6,-1,0
  4260.0    0.12       0  4340.2    0.05       0  4826.1    0.12       0
  4991.9    0.07       0  4995.9    0.12       0  5230.9    0.05       0
Bank Sta=4991.9,4995.9
Exp/Cntr=0.3,0.1

Type RM Length L Ch R = 1,4500,179,179,179
BEGIN DESCRIPTION:
DRY BRANCH 9.0
END DESCRIPTION:
XS GIS Cut Line= 3
      2902255.73     10161403.10      2903086.27     10161226.07
      2903505.70     10160703.09
#Sta/Elev= 30
  4150.8  953.12  4225.1  953.32  4363.5  946.99  4477.9  939.00  4641.5  935.22
  4754.7  935.49  4815.4  934.42  4848.7  935.55  4927.8  935.40  4968.7  930.91
  4985.4  927.63  4990.2  925.31  4990.5  924.81  4994.3  925.31  5003.5  926.43
  5023.0  933.29  5037.4  933.85  5043.8  932.11  5051.8  932.82  5058.2  931.70
  5101.4  935.17  5179.9  938.59  5200.7  940.96  5250.3  941.76  5307.9  944.56
  5407.1  952.02  5435.9  952.82  5491.9  956.98  5578.3  959.91  5670.4  966.00
#Mann=5,-1,0
  4150.8    0.05       0  4641.5    0.12       0  4985.4    0.05       0
  4990.2    0.03       0  4994.3    0.05       0
Bank Sta=4990.2,4994.3
Exp/Cntr=0.3,0.1

Type RM Length L Ch R = 1,4321,321,321,321
BEGIN DESCRIPTION:
Mapping XS 1021a43a
END DESCRIPTION:
XS GIS Cut Line= 3
      2902665.12     10161508.92      2903170.31     10161363.09
      2903632.24     10161124.34
#Sta/Elev= 30
  4413.3  947.71  4445.1  947.32  4456.5  945.97  4484.9  944.64  4529.0  941.01
  4642.9  933.65  4668.7  932.71  4713.2  933.31  4813.7  932.46  4925.0  933.78
  4939.1  933.27  4966.9  930.40  4989.0  925.53  4992.6  925.46  4992.9  924.96
  4996.7  925.46  5011.2  926.57  5024.0  931.31  5031.6  933.19  5046.5  935.86
  5077.6  937.87  5127.5  937.50  5144.1  940.02  5149.7  939.25  5166.2  940.57
  5171.8  939.64  5204.1  942.79  5276.9  945.75  5372.9  952.19  5459.1  956.14
#Mann=5,-1,0
  4413.3    0.05       0  4713.2    0.12       0  4992.6    0.07       0
  4996.7    0.12       0  5031.6    0.05       0
Bank Sta=4992.6,4996.7
Exp/Cntr=0.3,0.1

Type RM Length L Ch R = 1,4000,500,500,500
BEGIN DESCRIPTION:
DRY BRANCH 8.0
END DESCRIPTION:
XS GIS Cut Line= 3
      2902755.70     10161603.11      2903124.83     10161628.45
      2903505.70     10161453.10
#Sta/Elev= 30
  4630.0  947.81  4680.1  943.20  4699.1  940.15  4730.2  936.72  4780.3  933.17
  4840.5  931.25  4887.9  931.28  4940.7  931.16  4950.7  930.51  4960.8  929.08
  4970.8  926.31  4990.4  924.47  4993.4  922.79  4993.6  922.29  4997.5  922.79
  5011.9  923.98  5026.6  927.72  5034.0  930.40  5044.1  931.26  5056.0  930.80
  5089.0  932.09  5133.0  937.18  5169.9  939.90  5192.9  940.54  5256.2  944.14
  5307.7  947.73  5313.2  947.04  5336.1  947.61  5364.6  949.56  5419.3  950.61
#Mann=5,-1,0
  4630.0    0.05       0  4887.9    0.12       0  4993.4    0.07       0
  4997.5    0.12       0  5256.2    0.05       0
Bank Sta=4993.4,4997.5
Exp/Cntr=0.3,0.1