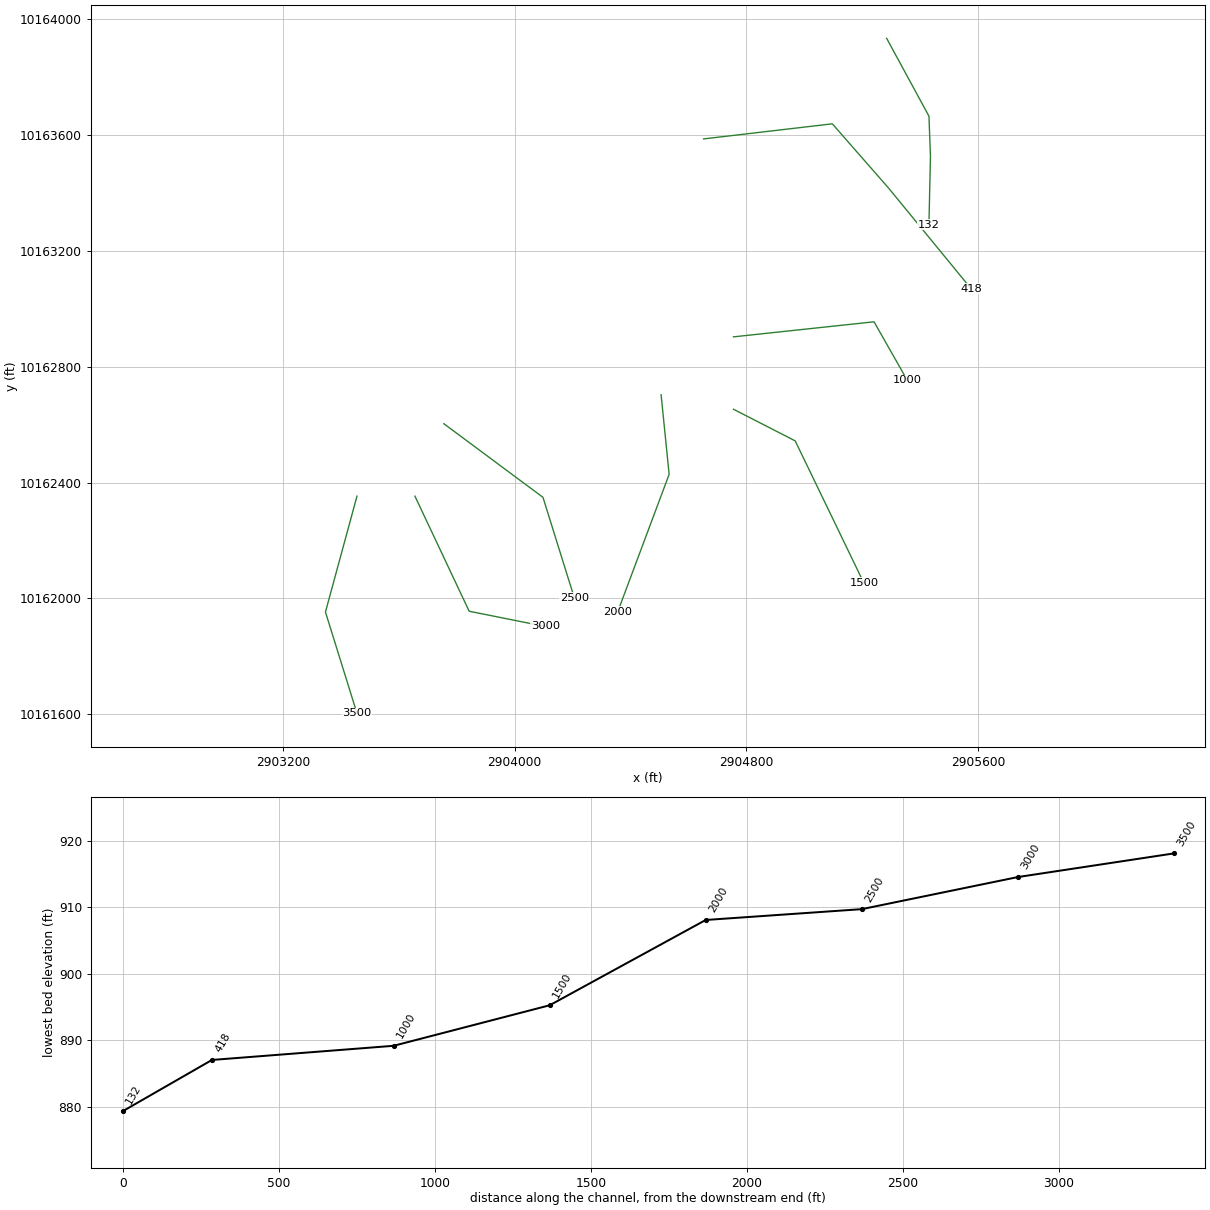
HEC-RAS study DRY BRANCH.prj: DRY BRANCH Base Level Engineering

--- DRY BRANCH.g01 (geometry) --- (continued)

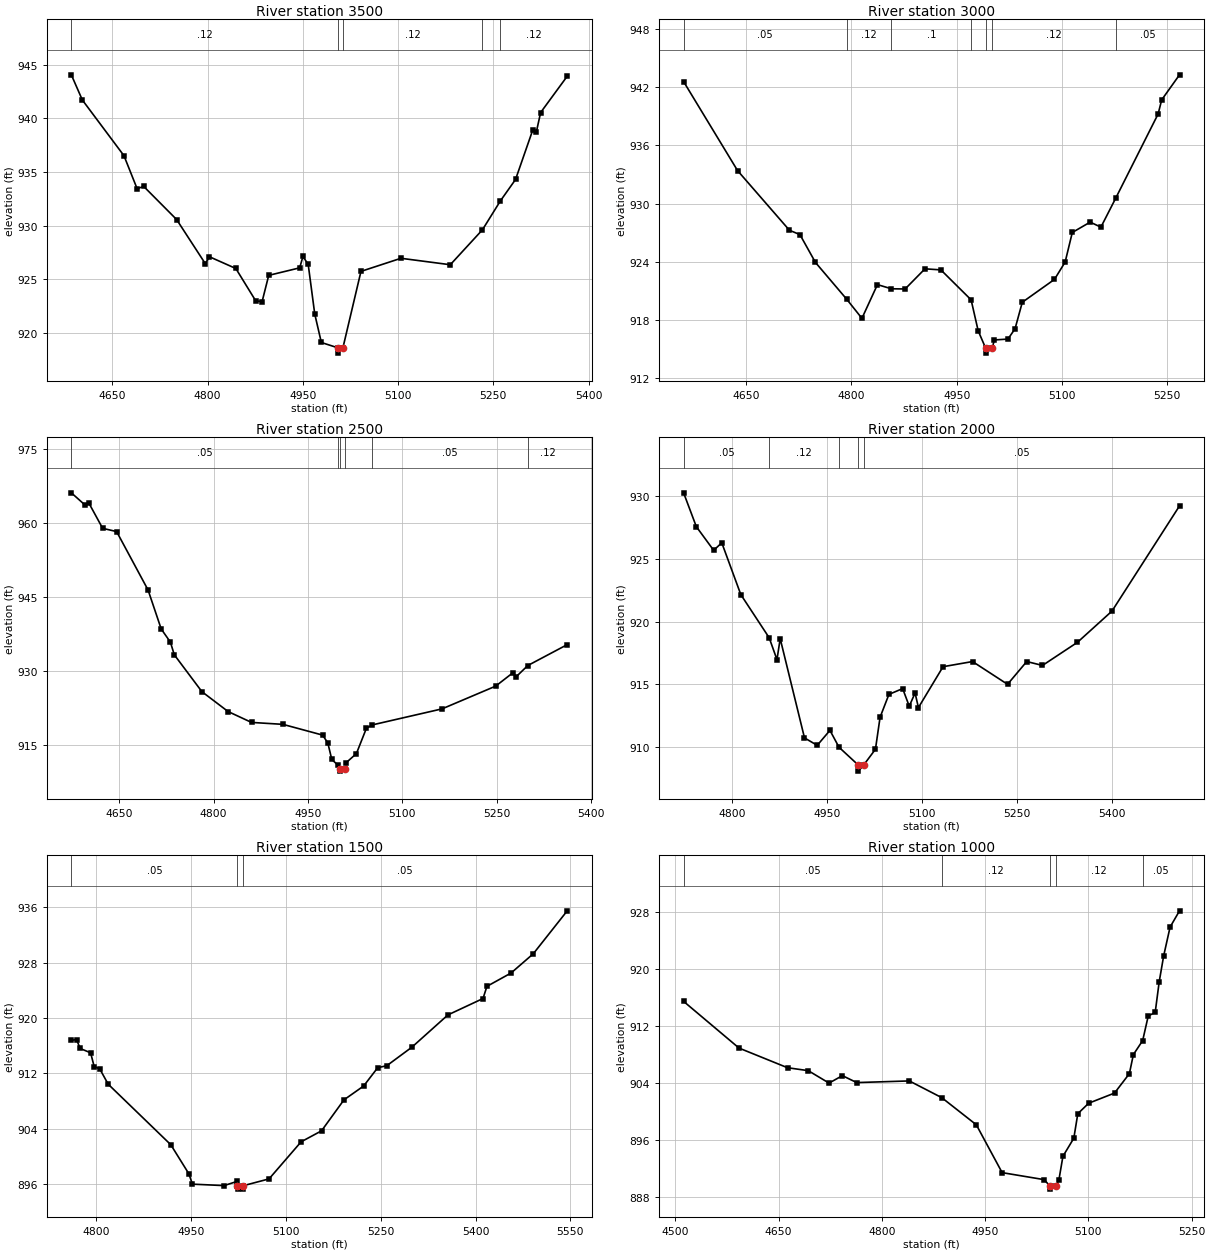
Type RM Length L Ch R = 1,3500,500,500,500
BEGIN DESCRIPTION:
DRY BRANCH 7.0
END DESCRIPTION:
XS GIS Cut Line= 3
      2903455.68     10162353.09      2903346.82     10161953.04
      2903455.69     10161603.08
#Sta/Elev= 30
  4585.4  944.04  4602.7  941.70  4668.3  936.51  4689.0  933.44  4699.4  933.65
  4751.2  930.57  4796.3  926.47  4803.0  927.10  4844.5  926.01  4875.9  922.99
  4885.9  922.93  4896.3  925.37  4945.1  926.07  4950.2  927.13  4958.5  926.39
  4968.8  921.77  4979.2  919.12  5005.0  918.63  5005.5  918.13  5013.2  918.63
  5041.6  925.74  5104.6  926.96  5182.3  926.36  5232.9  929.61  5261.3  932.31
  5285.1  934.30  5312.4  938.94  5317.7  938.68  5324.6  940.53  5366.5  943.91
#Mann=5,-1,0
  4585.4    0.12       0  5005.0    0.07       0  5013.2    0.12       0
  5232.9    0.05       0  5261.3    0.12       0
Bank Sta=5005,5013.2
Exp/Cntr=0.3,0.1

Type RM Length L Ch R = 1,3000,500,500,500
BEGIN DESCRIPTION:
DRY BRANCH 6.0
END DESCRIPTION:
XS GIS Cut Line= 3
      2903655.67     10162353.14      2903843.05     10161955.69
      2904105.64     10161903.12
#Sta/Elev= 30
  4560.6  942.59  4637.6  933.40  4711.5  927.25  4726.5  926.80  4748.6  923.93
  4793.1  920.14  4814.9  918.16  4837.0  921.64  4857.0  921.21  4876.5  921.19
  4904.8  923.27  4927.5  923.16  4970.6  920.07  4980.7  916.87  4991.4  915.07
  4991.9  914.57  5000.4  915.07  5003.9  915.93  5023.1  916.02  5033.3  917.09
  5043.6  919.82  5089.5  922.18  5104.7  923.97  5114.9  927.02  5140.4  928.09
  5155.7  927.57  5176.9  930.57  5237.3  939.25  5242.4  940.71  5267.8  943.29
#Mann=7,-1,0
  4560.6    0.05       0  4793.1    0.12       0  4857.0     0.1       0
  4970.6    0.12       0  4991.4    0.07       0  5000.4    0.12       0
  5176.9    0.05       0
Bank Sta=4991.4,5000.4
Exp/Cntr=0.3,0.1

Type RM Length L Ch R = 1,2500,500,500,500
BEGIN DESCRIPTION:
DRY BRANCH 5.0
END DESCRIPTION:
XS GIS Cut Line= 3
      2903755.71     10162603.10      2904097.79     10162349.05
      2904205.69     10162003.09
#Sta/Elev= 30
  4573.9  966.19  4595.8  963.70  4602.0  964.06  4623.7  958.99  4645.9  958.33
  4695.9  946.48  4716.8  938.57  4731.4  935.91  4737.6  933.34  4781.5  925.86
  4823.1  921.83  4860.4  919.62  4910.2  919.23  4973.4  917.05  4981.7  915.47
  4988.0  912.12  4997.5  910.98  5000.8  910.24  5001.3  909.74  5009.8  910.24
  5010.6  911.42  5027.2  913.30  5043.1  918.45  5052.6  919.12  5163.4  922.37
  5248.6  926.98  5275.9  929.68  5281.1  928.87  5299.7  931.16  5362.4  935.40
#Mann=6,-1,0
  4573.9    0.05       0  4997.5    0.12       0  5000.8    0.07       0
  5009.8    0.12       0  5052.6    0.05       0  5299.7    0.12       0
Bank Sta=5000.8,5009.8
Exp/Cntr=0.3,0.1

Type RM Length L Ch R = 1,2000,500,500,500
BEGIN DESCRIPTION:
DRY BRANCH 4.0
END DESCRIPTION:
XS GIS Cut Line= 3
      2904505.69     10162703.10      2904533.41     10162428.40
      2904355.69     10161953.14
#Sta/Elev= 30
  4723.9  930.23  4744.0  927.54  4771.4  925.66  4784.2  926.26  4814.3  922.14
  4859.1  918.71  4871.4  916.97  4876.5  918.64  4914.9  910.75  4935.0  910.16
  4955.1  911.35  4969.4  910.01  4999.5  908.61  5000.0  908.11  5008.6  908.61
  5027.0  909.85  5034.3  912.39  5048.3  914.21  5070.0  914.67  5080.4  913.27
  5089.6  914.32  5094.9  913.16  5133.8  916.41  5180.4  916.82  5235.7  915.01
  5266.0  916.82  5290.9  916.51  5346.2  918.35  5400.7  920.83  5507.4  929.19
#Mann=5,-1,0
  4723.9    0.05       0  4859.1    0.12       0  4969.4    0.05       0
  4999.5    0.05       0  5008.6    0.05       0
Bank Sta=4999.5,5008.6
Exp/Cntr=0.3,0.1

Type RM Length L Ch R = 1,1500,500,500,500
BEGIN DESCRIPTION:
DRY BRANCH 3.0
END DESCRIPTION:
XS GIS Cut Line= 3
      2904755.71     10162653.10      2904968.66     10162543.92
      2905205.66     10162053.15
#Sta/Elev= 30
  4760.7  916.79  4769.0  916.89  4774.6  915.61  4791.2  914.98  4796.8  912.99
  4805.6  912.66  4819.0  910.44  4918.0  901.69  4946.5  897.50  4952.2  895.99
  5002.3  895.78  5022.6  896.38  5023.5  895.77  5024.0  895.27  5032.3  895.27
  5032.8  895.77  5073.4  896.75  5124.1  902.11  5156.4  903.70  5191.9  908.18
  5223.0  910.18  5245.2  912.82  5259.7  913.12  5299.4  915.80  5356.3  920.46
  5411.8  922.83  5418.0  924.59  5456.2  926.52  5491.3  929.30  5545.0  935.51
#Mann=3,-1,0
  4760.7    0.05       0  5023.5    0.03       0  5032.8    0.05       0
Bank Sta=5023.5,5032.8
Exp/Cntr=0.3,0.1

Type RM Length L Ch R = 1,1000,582,582,582
BEGIN DESCRIPTION:
DRY BRANCH 2.0
END DESCRIPTION:
XS GIS Cut Line= 3
      2904755.68     10162903.11      2905240.81     10162955.05
      2905355.67     10162753.13
#Sta/Elev= 30
  4512.1  915.46  4592.6  908.92  4663.0  906.17  4693.1  905.76  4723.3  904.02
  4742.7  905.06  4763.5  904.09  4839.9  904.32  4887.0  901.98  4937.2  898.18
  4974.7  891.48  5035.6  890.50  5043.6  889.67  5044.1  889.17  5052.9  889.67
  5057.2  890.49  5063.0  893.77  5078.8  896.30  5084.6  899.73  5100.4  901.20
  5137.9  902.62  5159.5  905.34  5165.3  908.01  5178.8  909.97  5186.9  913.42
  5197.0  913.92  5202.8  918.20  5209.3  921.84  5218.6  925.86  5232.3  928.14
#Mann=5,-1,0
  4512.1    0.05       0  4887.0    0.12       0  5043.6    0.07       0
  5052.9    0.12       0  5178.8    0.05       0
Bank Sta=5043.6,5052.9
Exp/Cntr=0.3,0.1

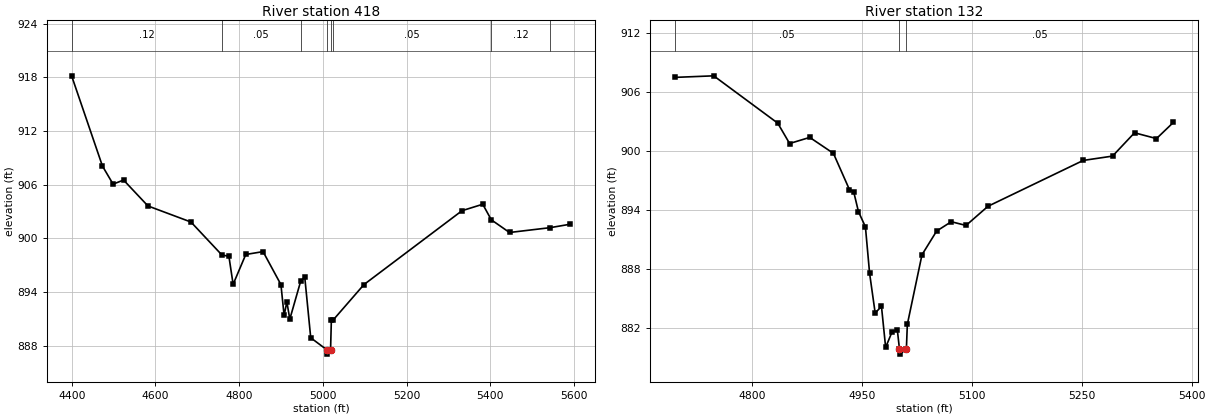
Type RM Length L Ch R = 1,418,286,286,286
BEGIN DESCRIPTION:
Mapping XS 0c6b4871
END DESCRIPTION:
XS GIS Cut Line= 4
      2904652.45     10163586.55      2905096.90     10163638.63
      2905291.35     10163416.41      2905576.06     10163069.20
#Sta/Elev= 30
  4399.6  918.18  4473.3  908.08  4498.7  906.06  4523.7  906.52  4582.0  903.62
  4684.8  901.82  4758.7  898.13  4775.4  897.99  4785.5  894.85  4815.7  898.19
  4857.0  898.51  4899.7  894.82  4907.3  891.37  4913.9  892.89  4920.9  890.95
  4946.9  895.20  4956.6  895.67  4970.9  888.87  5008.9  887.54  5009.4  887.04
  5018.3  887.54  5020.2  890.86  5024.7  890.87  5098.0  894.82  5332.4  903.09
  5381.9  903.81  5402.3  902.07  5445.8  900.65  5542.9  901.19  5591.4  901.58
#Mann=8,-1,0
  4399.6    0.12       0  4758.7    0.05       0  4946.9    0.12       0
  5008.9    0.07       0  5018.3    0.12       0  5024.7    0.05       0
  5402.3    0.12       0  5542.9     0.1       0
Bank Sta=5008.9,5018.3
Exp/Cntr=0.3,0.1

Type RM Length L Ch R = 1,132,0,0,0
BEGIN DESCRIPTION:
DRY BRANCH 1.0
END DESCRIPTION:
XS GIS Cut Line= 4
      2905284.41     10163933.76      2905430.50     10163665.00
      2905435.66     10163526.56      2905430.38     10163290.16
#Sta/Elev= 30
  4694.1  907.45  4747.6  907.61  4835.0  902.80  4851.2  900.73  4878.7  901.35
  4911.0  899.73  4932.9  896.04  4938.6  895.85  4945.2  893.80  4954.7  892.26
  4960.4  887.53  4968.0  883.50  4976.6  884.17  4982.3  880.00  4990.8  881.54
  4998.2  881.81  5001.2  879.82  5001.7  879.32  5010.6  879.82  5011.9  882.34
  5031.9  889.42  5051.9  891.83  5071.9  892.78  5092.0  892.40  5122.0  894.35
  5252.0  899.01  5292.0  899.45  5322.0  901.82  5352.0  901.23  5375.0  902.87
#Mann=3,-1,0
  4694.1    0.05       0  5001.2    0.03       0  5010.6    0.05       0
Bank Sta=5001.2,5010.6
Exp/Cntr=0.3,0.1

Chan Stop Cuts=-1