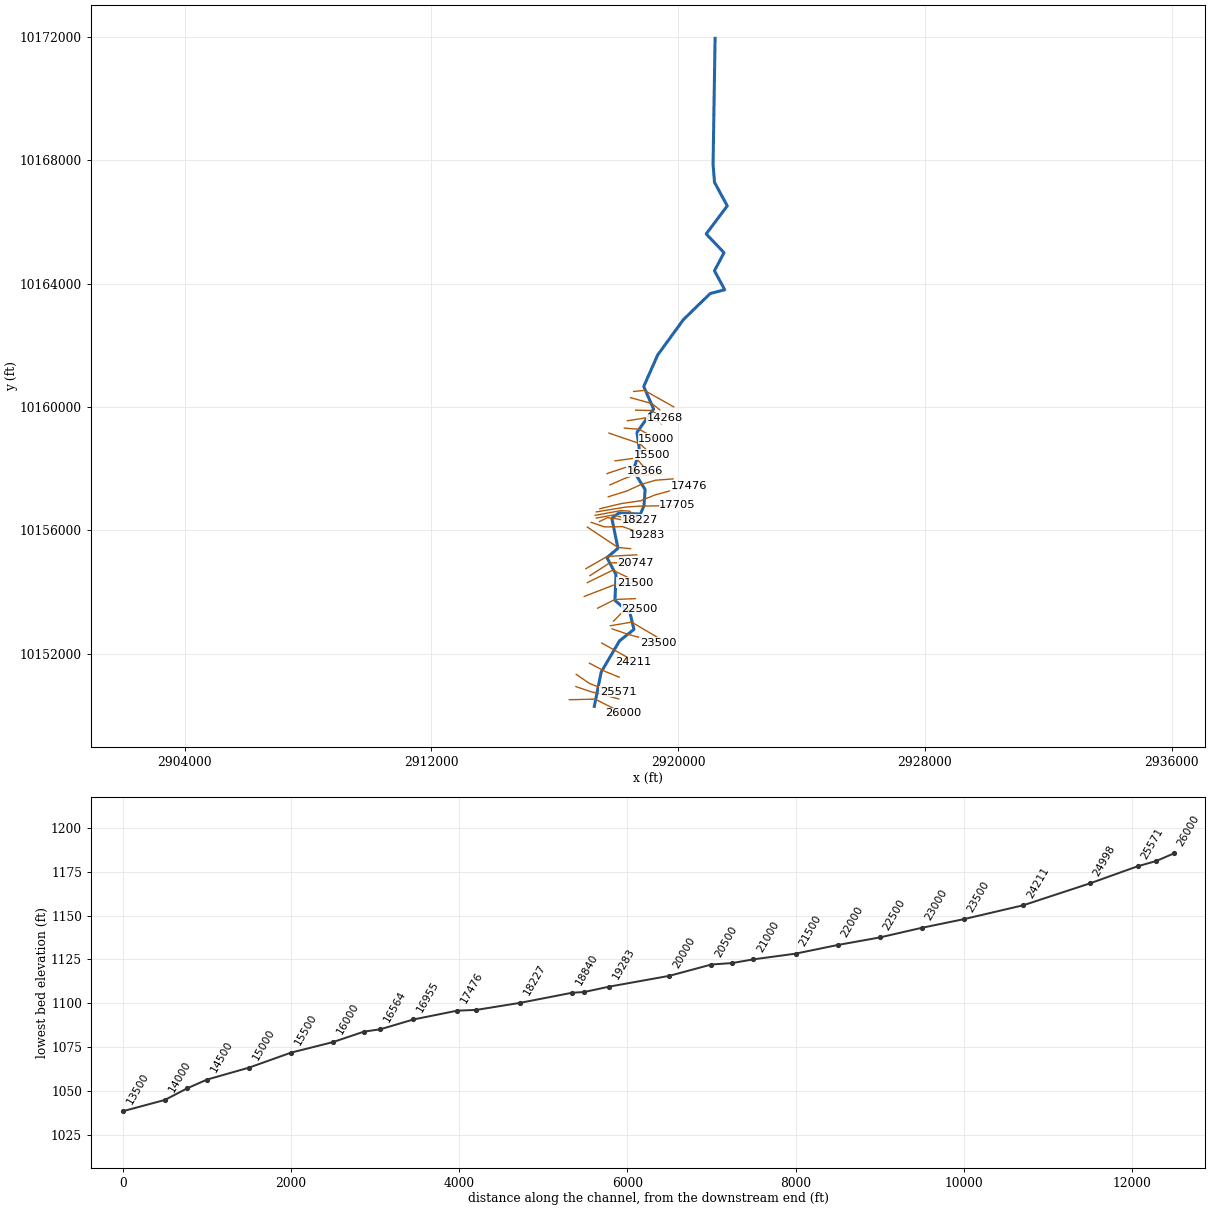
--- HORSESHOE CREEK.prj (project) ---

Proj Title=HORSESHOE CREEK Base Level Engineering
Current Plan=p01
Default Exp/Contr=0.3,0.1
English Units
Geom File=g01
Flow File=f01
Plan File=p01
Y Axis Title=Elevation
X Axis Title(PF)=Main Channel Distance
X Axis Title(XS)=Station
BEGIN DESCRIPTION:
HORSESHOE CREEK
END DESCRIPTION:
DSS Export Rating Curves= 0
DSS Export Rating Curve Sorted= 0
DSS Export Volume Flow Curves= 0
DXF OffsetX= 0
DXF OffsetY= 0
DXF ScaleX= 1
DXF ScaleY= 10

--- HORSESHOE CREEK.p01 (plan) ---

Plan Title=Multiple Run
Short Identifier=Multiple
Geom File=g01
Flow File=f01
Subcritical Flow
K Sum by GR= 0
Std Step Tol= 0.01
Critical Tol= 0.01
Num of Std Step Trials= 20
Max Error Tol= 0.3
Flow Tol Ratio= 0.001
Split Flow NTrial= 30
Split Flow Tol= 0.02
Split Flow Ratio= 0.02
Log Output Level= 0
Friction Slope Method= 1
Unsteady Friction Slope Method= 2
Unsteady Bridges Friction Slope Method= 1
Parabolic Critical Depth
Global Vel Dist=  1 , 1 , 1
Global Log Level= 0
CheckData=True
Encroach Param= -1, 0, 0, 0
BEGIN DESCRIPTION:
Multiple Run
END DESCRIPTION:

--- HORSESHOE CREEK.f01 (steady flow) ---

Flow Title=Multiple
Number of Profiles=7
Profile Names=10-year,25-year,50-year,1pct_min,100-year,1pct_plu,500-year
River Rch & RM= HORSESHOE CREEK,Reach-1,26000
     435     703     940     710    1251    2204    1714
River Rch & RM= HORSESHOE CREEK,Reach-1,17705
     915    1570    2751    1928    3899    7888    5576
River Rch & RM= HORSESHOE CREEK,Reach-1,4171
    1096    1900    3305    2296    4699    9617    6685
Boundary for River Rch & Prof#=HORSESHOE CREEK,Reach-1,1
Up Type=0
Dn Type=3
Dn Slope=0.005
Boundary for River Rch & Prof#=HORSESHOE CREEK,Reach-1,2
Up Type=0
Dn Type=3
Dn Slope=0.005
Boundary for River Rch & Prof#=HORSESHOE CREEK,Reach-1,3
Up Type=0
Dn Type=3
Dn Slope=0.005
Boundary for River Rch & Prof#=HORSESHOE CREEK,Reach-1,4
Up Type=0
Dn Type=3
Dn Slope=0.005
Boundary for River Rch & Prof#=HORSESHOE CREEK,Reach-1,5
Up Type=0
Dn Type=3
Dn Slope=0.005
Boundary for River Rch & Prof#=HORSESHOE CREEK,Reach-1,6
Up Type=0
Dn Type=3
Dn Slope=0.005
Boundary for River Rch & Prof#=HORSESHOE CREEK,Reach-1,7
Up Type=0
Dn Type=3
Dn Slope=0.005

--- HORSESHOE CREEK.g01 (geometry) ---

Geom Title=Existing Conditions

River Reach=HORSESHOE CREEK,Reach-1
Reach XY= 30
      2917281.00     10150288.00      2917504.25     10151401.00
      2918098.25     10152412.00      2918567.50     10152785.00
      2918440.00     10153307.00      2917950.25     10153726.00
      2917985.25     10154561.00      2917691.00     10155112.00
      2918047.50     10155416.00      2917849.75     10156391.00
      2918075.25     10156561.00      2918777.25     10156525.00
      2918892.00     10156807.00      2918928.50     10157322.00
      2918546.00     10157938.00      2918747.00     10158576.00
      2918664.25     10159180.00      2919203.25     10159934.00
      2918884.00     10160667.00      2919335.75     10161688.00
      2920171.50     10162836.00      2921037.00     10163680.00
      2921509.25     10163803.00      2921176.75     10164419.00
      2921486.50     10165006.00      2920908.50     10165614.00
      2921592.25     10166523.00      2921178.50     10167288.00
      2921131.50     10167866.00      2921196.75     10171960.00

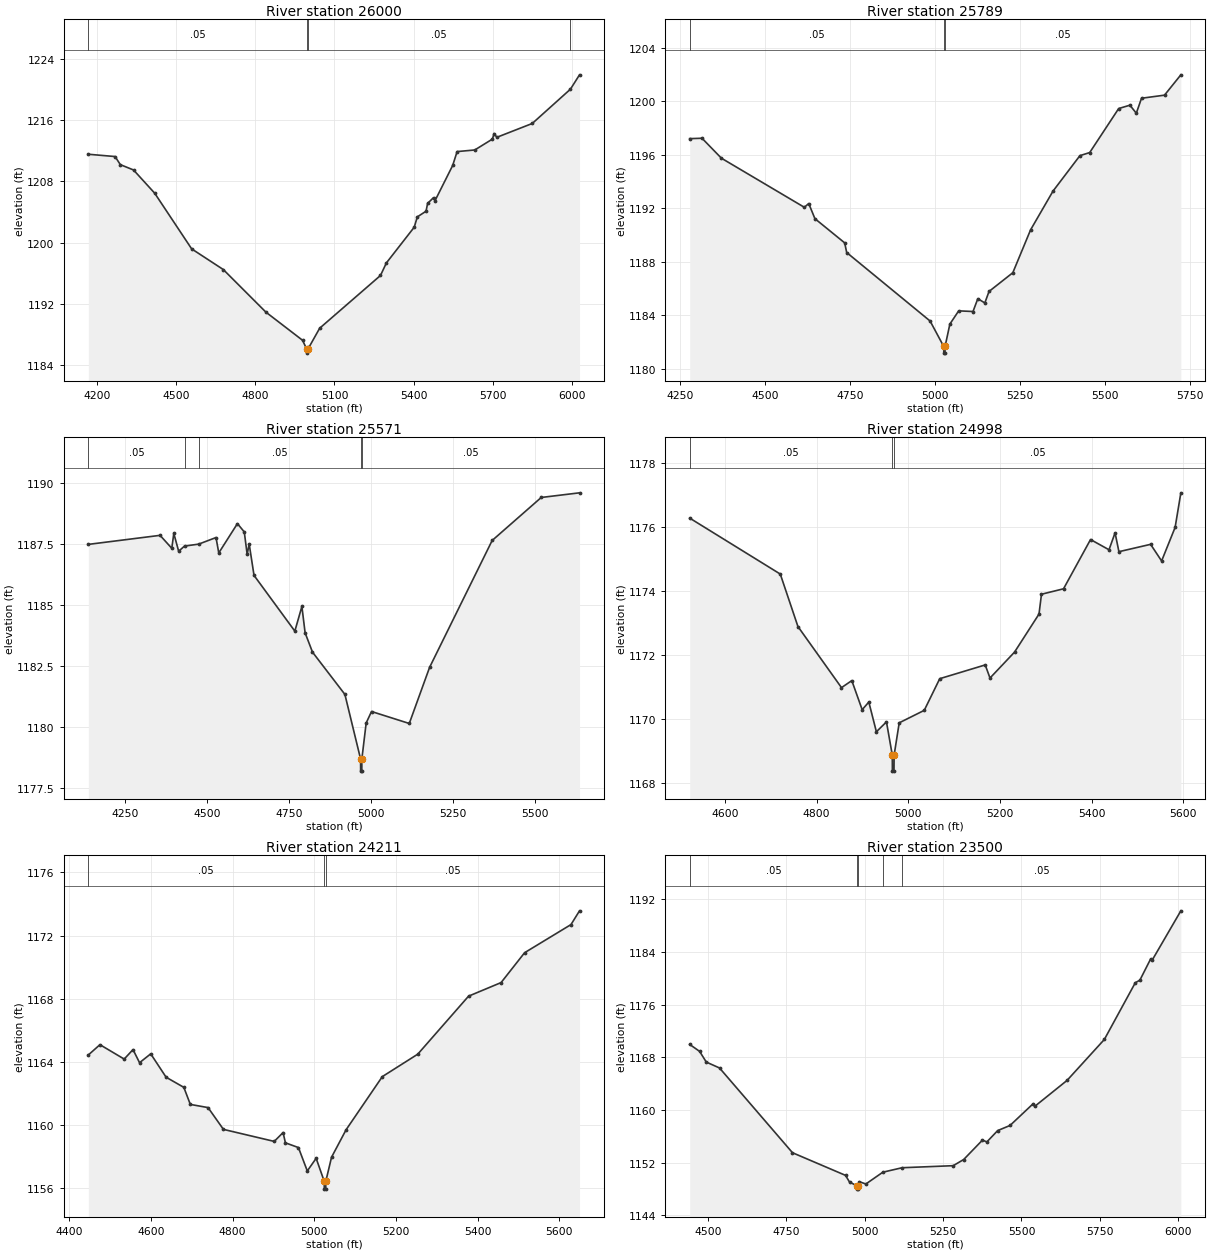
Type RM Length L Ch R = 1,26000,211,211,211
BEGIN DESCRIPTION:
HORSESHOE CREEK 52.0
END DESCRIPTION:
XS GIS Cut Line= 3
      2916474.48     10150503.36      2917306.48     10150521.72
      2918225.01     10150059.89
#Sta/Elev= 30
  4167.8 1211.56  4269.0 1211.26  4289.0 1210.20  4339.0 1209.50  4419.1 1206.46
  4559.1 1199.17  4679.1 1196.46  4840.2 1190.89  4979.2 1187.20  4995.1 1186.02
  4995.4 1185.52  4999.1 1186.02  5043.9 1188.78  5274.3 1195.69  5296.6 1197.33
  5402.1 1202.01  5413.8 1203.36  5446.8 1204.10  5452.8 1205.13  5475.2 1205.88
  5480.8 1205.48  5547.7 1210.09  5564.5 1211.91  5631.4 1212.12  5698.4 1213.55
  5704.3 1214.27  5715.1 1213.78  5849.1 1215.59  5993.7 1220.08  6028.1 1221.96
#Mann=4,-1,0
  4167.8    0.05       0  4995.1    0.03       0  4999.1    0.05       0
  5993.7    0.12       0
Bank Sta=4995.1,4999.1
Exp/Cntr=0.3,0.1

Type RM Length L Ch R = 1,25789,218,218,218
BEGIN DESCRIPTION:
Mapping XS 5e7656b7
END DESCRIPTION:
XS GIS Cut Line= 4
      2916684.55     10150929.32      2917157.19     10150765.94
      2917548.13     10150672.58      2918071.98     10150527.06
#Sta/Elev= 30
  4277.5 1197.19  4313.8 1197.22  4370.8 1195.73  4614.9 1192.06  4627.9 1192.34
  4646.1 1191.21  4733.7 1189.40  4739.6 1188.68  4985.1 1183.56  5025.2 1181.66
  5025.5 1181.16  5029.0 1181.16  5029.2 1181.66  5043.3 1183.33  5069.3 1184.32
  5111.4 1184.27  5125.6 1185.23  5146.2 1184.91  5158.6 1185.77  5228.6 1187.17
  5280.8 1190.37  5346.9 1193.27  5426.1 1195.92  5454.9 1196.15  5540.2 1199.44
  5573.2 1199.69  5592.1 1199.09  5607.4 1200.21  5675.1 1200.44  5723.2 1201.96
#Mann=3,-1,0
  4277.5    0.05       0  5025.2    0.05       0  5029.2    0.05       0
Bank Sta=5025.2,5029.2
Exp/Cntr=0.3,0.1

Type RM Length L Ch R = 1,25571,573,573,573
BEGIN DESCRIPTION:
Mapping XS ee6e7ccd
END DESCRIPTION:
XS GIS Cut Line= 6
      2916696.24     10151326.09      2917116.34     10151034.35
      2917338.07     10150946.82      2917542.30     10150882.64
      2917939.08     10150783.44      2918061.13     10150766.01
#Sta/Elev= 30
  4138.4 1187.49  4356.8 1187.86  4392.6 1187.33  4398.7 1187.94  4413.5 1187.21
  4431.3 1187.42  4474.4 1187.50  4527.3 1187.77  4535.7 1187.14  4592.5 1188.34
  4613.4 1188.00  4622.2 1187.08  4628.3 1187.51  4643.1 1186.22  4767.4 1183.94
  4788.9 1184.95  4798.7 1183.87  4821.2 1183.08  4919.9 1181.35  4967.6 1178.71
  4967.9 1178.21  4971.4 1178.21  4971.6 1178.71  4984.7 1180.18  5001.0 1180.65
  5116.0 1180.16  5178.0 1182.46  5368.5 1187.65  5518.0 1189.41  5634.6 1189.60
#Mann=5,-1,0
  4138.4    0.05       0  4431.3    0.12       0  4474.4    0.05       0
  4967.6    0.03       0  4971.6    0.05       0
Bank Sta=4967.6,4971.6
Exp/Cntr=0.3,0.1

Type RM Length L Ch R = 1,24998,787,787,787
BEGIN DESCRIPTION:
Mapping XS 4037ce04
END DESCRIPTION:
XS GIS Cut Line= 3
      2917122.21     10151687.85      2917647.33     10151413.63
      2918090.75     10151232.76
#Sta/Elev= 30
  4523.4 1176.27  4721.0 1174.52  4759.5 1172.88  4854.5 1170.97  4877.0 1171.19
  4899.6 1170.28  4914.1 1170.52  4930.6 1169.59  4952.6 1169.90  4965.3 1168.86
  4965.5 1168.36  4969.0 1168.36  4969.3 1168.86  4980.4 1169.87  5035.0 1170.26
  5068.8 1171.25  5168.0 1171.68  5178.4 1171.27  5231.9 1172.08  5285.3 1173.27
  5290.7 1173.89  5338.8 1174.06  5397.7 1175.60  5438.0 1175.28  5451.2 1175.81
  5459.6 1175.22  5528.7 1175.45  5552.7 1174.93  5582.2 1175.98  5594.7 1177.06
#Mann=3,-1,0
  4523.4    0.05       0  4965.3    0.05       0  4969.3    0.05       0
Bank Sta=4965.3,4969.3
Exp/Cntr=0.3,0.1

Type RM Length L Ch R = 1,24211,711,711,711
BEGIN DESCRIPTION:
Mapping XS a7aa2094
END DESCRIPTION:
XS GIS Cut Line= 3
      2917524.81     10152341.39      2918347.53     10151880.43
      2918550.59     10151717.98
#Sta/Elev= 30
  4446.5 1164.45  4474.9 1165.10  4534.3 1164.19  4555.9 1164.79  4571.9 1163.96
  4599.3 1164.52  4637.0 1163.04  4680.4 1162.40  4696.3 1161.32  4739.7 1161.12
  4777.4 1159.74  4901.8 1158.98  4923.5 1159.54  4929.2 1158.89  4961.1 1158.59
  4982.8 1157.11  5004.5 1157.91  5024.2 1156.46  5024.5 1155.96  5028.0 1155.96
  5028.2 1156.46  5042.2 1157.98  5077.9 1159.72  5166.6 1163.08  5253.4 1164.50
  5377.8 1168.17  5457.5 1169.03  5515.1 1170.92  5628.7 1172.70  5649.6 1173.57
#Mann=3,-1,0
  4446.5    0.05       0  5024.2    0.05       0  5028.2    0.05       0
Bank Sta=5024.2,5028.2
Exp/Cntr=0.3,0.1

Type RM Length L Ch R = 1,23500,500,500,500
BEGIN DESCRIPTION:
HORSESHOE CREEK 47.0
END DESCRIPTION:
XS GIS Cut Line= 3
      2917855.67     10152803.11      2918383.66     10152621.34
      2919355.73     10152353.10
#Sta/Elev= 30
  4441.6 1169.96  4473.3 1168.90  4494.5 1167.28  4536.8 1166.38  4769.5 1153.51
  4938.7 1150.07  4951.5 1149.05  4975.5 1148.48  4975.7 1147.98  4979.2 1147.98
  4979.5 1148.48  4982.7 1149.11  5003.6 1148.76  5057.7 1150.55  5119.2 1151.23
  5282.2 1151.54  5315.7 1152.48  5375.6 1155.43  5389.6 1155.15  5424.0 1156.87
  5463.5 1157.65  5537.4 1160.96  5542.6 1160.56  5645.3 1164.49  5764.3 1170.71
  5863.1 1179.33  5877.7 1179.72  5912.1 1182.95  5917.3 1182.79  6008.4 1190.25
#Mann=5,-1,0
  4441.6    0.05       0  4975.5    0.05       0  4979.5    0.05       0
  5057.7    0.12       0  5119.2    0.05       0
Bank Sta=4975.5,4979.5
Exp/Cntr=0.3,0.1

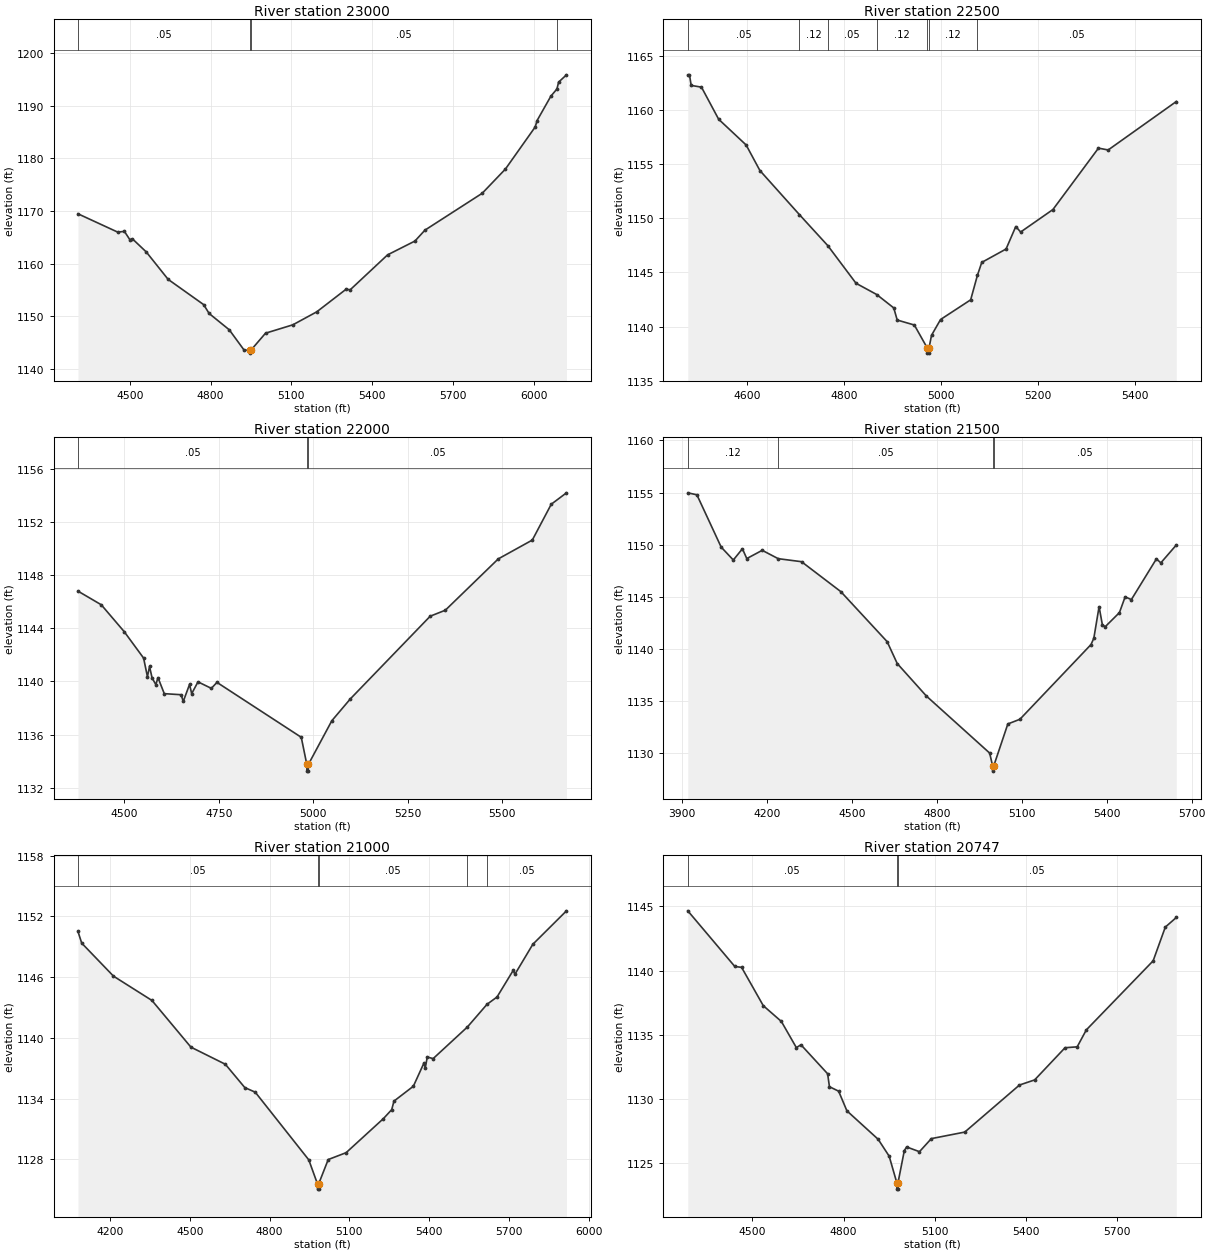
Type RM Length L Ch R = 1,23000,500,500,500
BEGIN DESCRIPTION:
HORSESHOE CREEK 46.0
END DESCRIPTION:
XS GIS Cut Line= 3
      2917805.67     10152903.11      2918488.34     10153020.54
      2919455.70     10152453.11
#Sta/Elev= 30
  4307.3 1169.47  4454.6 1166.00  4479.8 1166.13  4500.1 1164.55  4509.5 1164.72
  4561.0 1162.23  4642.2 1157.03  4774.1 1152.24  4794.4 1150.56  4869.1 1147.47
  4923.9 1143.64  4944.6 1143.54  4944.8 1143.04  4948.6 1143.54  5003.8 1146.82
  5105.3 1148.41  5194.0 1150.87  5302.7 1155.15  5318.4 1155.06  5457.1 1161.68
  5558.7 1164.30  5595.9 1166.37  5808.5 1173.36  5894.8 1177.96  6005.6 1185.96
  6012.1 1187.14  6063.5 1191.78  6086.1 1193.15  6092.2 1194.44  6121.5 1195.83
#Mann=4,-1,0
  4307.3    0.05       0  4944.6    0.05       0  4948.6    0.05       0
  6086.1    0.12       0
Bank Sta=4944.6,4948.6
Exp/Cntr=0.3,0.1

Type RM Length L Ch R = 1,22500,500,500,500
BEGIN DESCRIPTION:
HORSESHOE CREEK 45.0
END DESCRIPTION:
XS GIS Cut Line= 3
      2917905.71     10153053.14      2918271.86     10153424.34
      2918755.71     10153453.11
#Sta/Elev= 30
  4478.6 1163.28  4482.1 1163.28  4485.6 1162.30  4506.8 1162.14  4542.2 1159.17
  4598.8 1156.79  4627.1 1154.43  4708.3 1150.36  4767.0 1147.48  4825.1 1144.00
  4867.7 1142.96  4902.8 1141.72  4909.9 1140.60  4945.2 1140.14  4971.5 1138.04
  4971.8 1137.54  4975.3 1137.54  4975.5 1138.04  4980.6 1139.19  4999.2 1140.65
  5061.2 1142.47  5075.0 1144.72  5084.0 1145.93  5134.1 1147.17  5154.1 1149.25
  5164.1 1148.74  5230.6 1150.82  5324.4 1156.50  5344.4 1156.33  5484.7 1160.81
#Mann=7,-1,0
  4478.6    0.05       0  4708.3    0.12       0  4767.0    0.05       0
  4867.7    0.12       0  4971.5    0.07       0  4975.5    0.12       0
  5075.0    0.05       0
Bank Sta=4971.5,4975.5
Exp/Cntr=0.3,0.1

Type RM Length L Ch R = 1,22000,500,500,500
BEGIN DESCRIPTION:
HORSESHOE CREEK 44.0
END DESCRIPTION:
XS GIS Cut Line= 3
      2917390.56     10153473.38      2917946.59     10153753.70
      2918615.97     10153782.65
#Sta/Elev= 30
  4377.3 1146.81  4439.0 1145.78  4499.8 1143.75  4551.0 1141.76  4561.1 1140.36
  4566.7 1141.13  4573.4 1140.27  4583.4 1139.76  4589.0 1140.29  4605.7 1139.08
  4650.3 1139.00  4655.9 1138.49  4672.6 1139.78  4678.2 1139.08  4694.9 1139.97
  4730.2 1139.48  4745.1 1139.93  4968.2 1135.79  4982.9 1133.74  4983.1 1133.24
  4986.6 1133.24  4986.9 1133.74  5049.1 1137.04  5098.2 1138.69  5309.4 1144.92
  5349.4 1145.37  5489.5 1149.24  5579.6 1150.66  5629.7 1153.36  5670.0 1154.22
#Mann=3,-1,0
  4377.3    0.05       0  4982.9    0.05       0  4986.9    0.05       0
Bank Sta=4982.9,4986.9
Exp/Cntr=0.3,0.1

Type RM Length L Ch R = 1,21500,500,500,500
BEGIN DESCRIPTION:
HORSESHOE CREEK 43.0
END DESCRIPTION:
XS GIS Cut Line= 3
      2916955.70     10153853.12      2917962.70     10154243.17
      2918605.71     10154303.11
#Sta/Elev= 30
  3920.1 1154.98  3952.3 1154.79  4038.0 1149.78  4080.9 1148.54  4113.1 1149.62
  4128.5 1148.68  4183.0 1149.47  4239.6 1148.67  4321.9 1148.38  4460.8 1145.51
  4624.3 1140.72  4660.0 1138.62  4763.2 1135.50  4986.5 1130.04  4996.9 1128.81
  4997.2 1128.31  5000.9 1128.81  5050.7 1132.83  5093.4 1133.28  5344.5 1140.44
  5354.5 1141.05  5373.0 1144.07  5384.6 1142.34  5394.7 1142.15  5444.9 1143.50
  5465.0 1145.01  5487.1 1144.75  5575.5 1148.65  5591.2 1148.27  5645.8 1149.98
#Mann=4,-1,0
  3920.1    0.12       0  4239.6    0.05       0  4996.9    0.05       0
  5000.9    0.05       0
Bank Sta=4996.9,5000.9
Exp/Cntr=0.3,0.1

Type RM Length L Ch R = 1,21000,253,253,253
BEGIN DESCRIPTION:
HORSESHOE CREEK 42.0
END DESCRIPTION:
XS GIS Cut Line= 3
      2917055.64     10154303.09      2917882.74     10154707.56
      2918705.72     10154303.09
#Sta/Elev= 30
  4079.3 1150.51  4093.4 1149.36  4212.9 1146.10  4357.6 1143.70  4504.2 1139.09
  4633.7 1137.40  4706.8 1135.10  4746.3 1134.64  4947.6 1127.96  4980.5 1125.57
  4980.8 1125.07  4984.3 1125.07  4984.5 1125.57  5020.7 1127.99  5088.1 1128.67
  5228.6 1132.04  5259.6 1132.92  5268.0 1133.76  5341.0 1135.23  5380.4 1137.50
  5385.9 1137.06  5393.3 1138.11  5415.5 1137.96  5544.3 1141.08  5618.1 1143.32
  5655.7 1144.04  5716.4 1146.66  5723.1 1146.29  5790.5 1149.25  5917.0 1152.55
#Mann=5,-1,0
  4079.3    0.05       0  4980.5    0.05       0  4984.5    0.05       0
  5544.3    0.12       0  5618.1    0.05       0
Bank Sta=4980.5,4984.5
Exp/Cntr=0.3,0.1

Type RM Length L Ch R = 1,20747,247,247,247
BEGIN DESCRIPTION:
Mapping XS 7de65437
END DESCRIPTION:
XS GIS Cut Line= 3
      2917136.84     10154526.75      2917782.68     10154943.43
      2918621.86     10154950.36
#Sta/Elev= 30
  4287.5 1144.66  4442.2 1140.32  4464.6 1140.25  4536.0 1137.26  4595.5 1136.03
  4644.8 1133.99  4660.0 1134.21  4747.7 1131.95  4753.7 1130.94  4784.0 1130.59
  4811.1 1129.06  4914.0 1126.84  4950.3 1125.52  4975.4 1123.45  4975.7 1122.95
  4979.2 1122.95  4979.4 1123.45  5000.2 1125.96  5007.8 1126.24  5050.0 1125.87
  5089.1 1126.89  5199.1 1127.40  5379.1 1131.07  5429.1 1131.47  5529.1 1133.98
  5569.1 1134.05  5599.1 1135.37  5819.1 1140.76  5859.1 1143.39  5895.3 1144.14
#Mann=3,-1,0
  4287.5    0.05       0  4975.4    0.05       0  4979.4    0.05       0
Bank Sta=4975.4,4979.4
Exp/Cntr=0.3,0.1

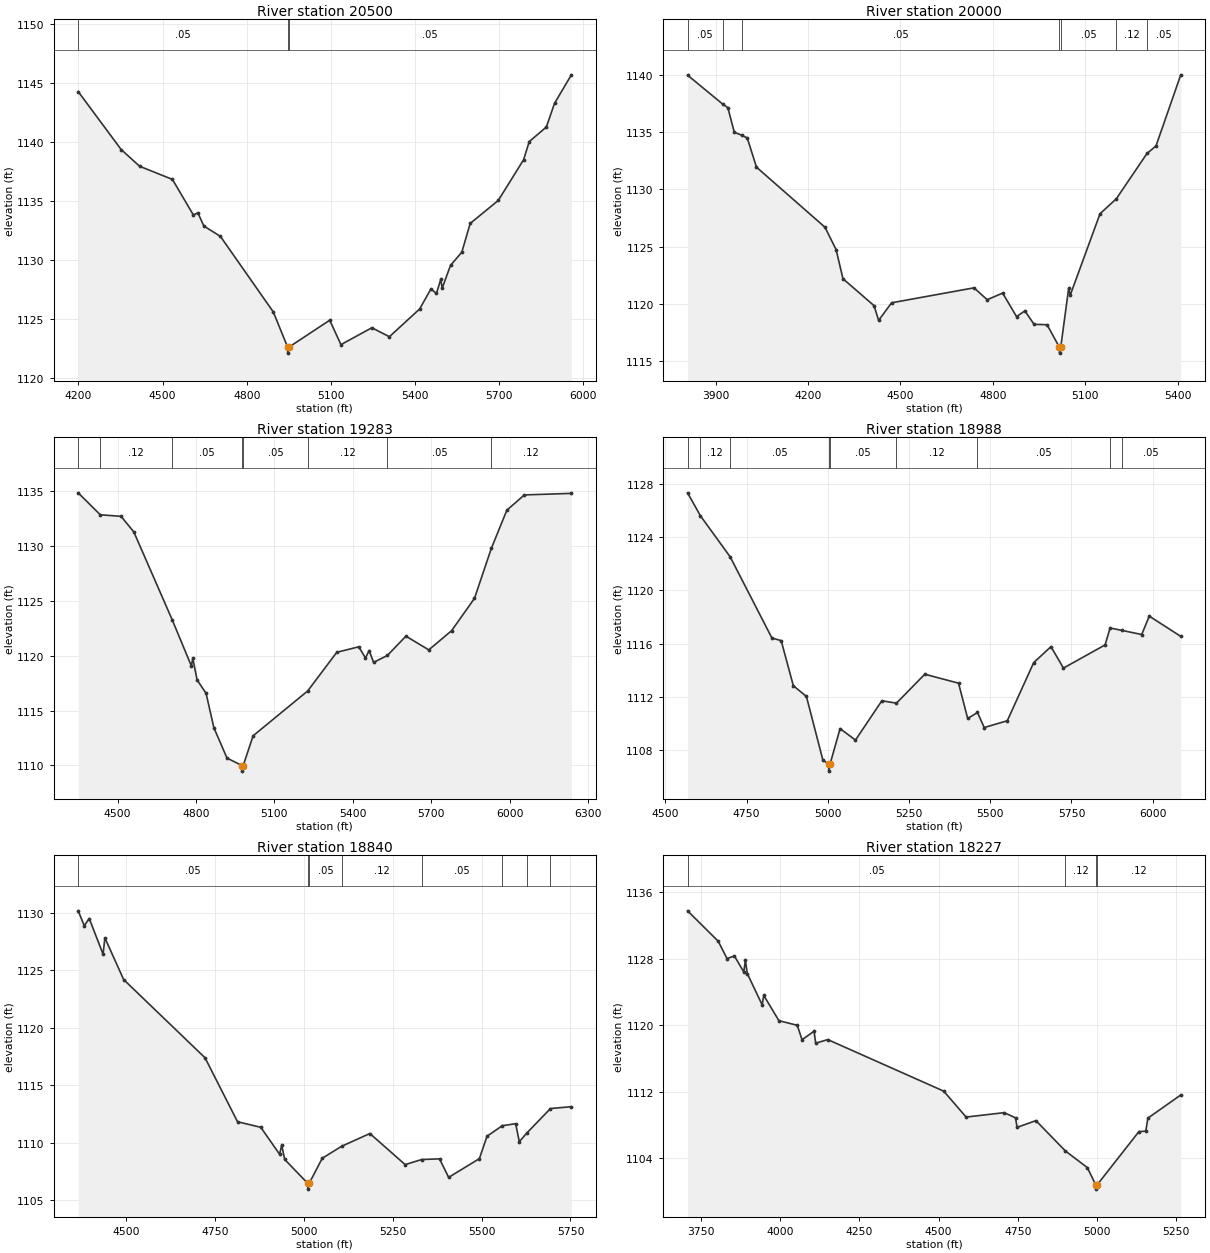
Type RM Length L Ch R = 1,20500,500,500,500
BEGIN DESCRIPTION:
HORSESHOE CREEK 41.0
END DESCRIPTION:
XS GIS Cut Line= 3
      2917005.70     10154753.12      2917700.15     10155151.69
      2918655.66     10155203.11
#Sta/Elev= 30
  4199.3 1144.28  4352.4 1139.37  4418.4 1137.95  4535.1 1136.84  4609.9 1133.82
  4625.7 1134.01  4647.2 1132.89  4706.2 1132.01  4894.6 1125.61  4945.8 1122.62
  4946.1 1122.12  4949.8 1122.62  5095.7 1124.91  5135.7 1122.84  5245.9 1124.27
  5308.3 1123.51  5416.1 1125.86  5456.2 1127.55  5476.2 1127.18  5491.5 1128.38
  5496.5 1127.63  5526.3 1129.56  5566.4 1130.67  5596.4 1133.11  5696.5 1135.06
  5786.7 1138.51  5806.7 1140.04  5867.8 1141.28  5896.8 1143.28  5956.9 1145.70
#Mann=3,-1,0
  4199.3    0.05       0  4945.8    0.05       0  4949.8    0.05       0
Bank Sta=4945.8,4949.8
Exp/Cntr=0.3,0.1

Type RM Length L Ch R = 1,20000,717,717,717
BEGIN DESCRIPTION:
HORSESHOE CREEK 40.0
END DESCRIPTION:
XS GIS Cut Line= 3
      2917055.72     10156103.09      2918047.10     10155442.88
      2918455.67     10155403.11
#Sta/Elev= 30
  3808.9 1140.01  3923.2 1137.47  3939.6 1137.17  3960.6 1135.01  3984.4 1134.75
  4002.7 1134.51  4032.7 1131.95  4255.1 1126.69  4291.2 1124.73  4313.5 1122.18
  4414.4 1119.82  4429.4 1118.53  4471.5 1120.07  4739.0 1121.38  4782.0 1120.34
  4832.1 1120.92  4877.2 1118.86  4904.3 1119.36  4934.3 1118.18  4976.4 1118.15
  5016.7 1116.16  5016.9 1115.66  5020.7 1116.16  5046.5 1121.35  5051.5 1120.73
  5148.3 1127.87  5201.2 1129.18  5300.8 1133.15  5330.1 1133.81  5410.5 1140.04
#Mann=7,-1,0
  3808.9    0.05       0  3923.2    0.12       0  3984.4    0.05       0
  5016.7    0.05       0  5020.7    0.05       0  5201.2    0.12       0
  5300.8    0.05       0
Bank Sta=5016.7,5020.7
Exp/Cntr=0.3,0.1

Type RM Length L Ch R = 1,19283,295,295,295
BEGIN DESCRIPTION:
Mapping XS 6678600b
END DESCRIPTION:
XS GIS Cut Line= 4
      2917180.52     10156256.71      2917612.32     10156110.83
      2918201.66     10156116.67      2918995.23     10155836.58
#Sta/Elev= 30
  4349.3 1134.82  4433.8 1132.82  4513.1 1132.68  4562.1 1131.26  4709.1 1123.25
  4782.3 1119.05  4787.6 1119.76  4804.2 1117.78  4838.4 1116.57  4868.4 1113.43
  4918.5 1110.67  4976.5 1109.98  4976.7 1109.48  4980.5 1109.98  5018.5 1112.70
  5227.3 1116.78  5338.5 1120.30  5422.7 1120.80  5448.3 1119.78  5462.3 1120.46
  5479.3 1119.38  5532.1 1120.01  5603.0 1121.77  5690.5 1120.52  5777.9 1122.27
  5865.3 1125.21  5929.9 1129.77  5989.2 1133.24  6056.3 1134.63  6236.0 1134.77
#Mann=8,-1,0
  4349.3     0.1       0  4433.8    0.12       0  4709.1    0.05       0
  4976.5    0.05       0  4980.5    0.05       0  5227.3    0.12       0
  5532.1    0.05       0  5929.9    0.12       0
Bank Sta=4976.5,4980.5
Exp/Cntr=0.3,0.1

Type RM Length L Ch R = 1,18988,148,148,148
BEGIN DESCRIPTION:
Mapping XS c4308049
END DESCRIPTION:
XS GIS Cut Line= 4
      2917449.34     10156283.70      2917706.29     10156408.70
      2917949.35     10156380.93      2918921.09     10156207.40
#Sta/Elev= 30
  4568.7 1127.31  4608.1 1125.59  4699.7 1122.51  4828.1 1116.42  4856.7 1116.22
  4894.1 1112.84  4934.4 1112.03  4984.7 1107.29  5002.8 1106.93  5003.1 1106.43
  5006.8 1106.93  5037.9 1109.62  5085.3 1108.76  5166.5 1111.71  5211.4 1111.53
  5298.5 1113.70  5402.4 1113.03  5430.6 1110.38  5460.7 1110.83  5481.4 1109.70
  5552.5 1110.21  5633.7 1114.57  5686.8 1115.77  5725.2 1114.16  5853.4 1115.90
  5868.7 1117.17  5904.7 1116.99  5966.1 1116.68  5989.3 1118.06  6086.2 1116.54
#Mann=9,-1,0
  4568.7     0.1       0  4608.1    0.12       0  4699.7    0.05       0
  5002.8    0.05       0  5006.8    0.05       0  5211.4    0.12       0
  5460.7    0.05       0  5868.7    0.12       0  5904.7    0.05       0
Bank Sta=5002.8,5006.8
Exp/Cntr=0.3,0.1

Type RM Length L Ch R = 1,18840,613,613,613
BEGIN DESCRIPTION:
Mapping XS 2b5697eb
END DESCRIPTION:
XS GIS Cut Line= 4
      2917345.13     10156394.81      2917907.68     10156498.98
      2918241.01     10156401.76      2918699.37     10156311.48
#Sta/Elev= 30
  4366.0 1130.15  4383.0 1128.86  4397.1 1129.48  4435.9 1126.38  4441.0 1127.80
  4493.8 1124.18  4722.5 1117.39  4814.0 1111.83  4879.3 1111.35  4932.2 1109.01
  4938.1 1109.81  4946.5 1108.56  5011.4 1106.48  5011.7 1105.98  5015.4 1106.48
  5052.1 1108.66  5106.5 1109.70  5186.0 1110.81  5285.2 1108.11  5331.6 1108.55
  5381.8 1108.61  5407.5 1107.00  5493.9 1108.63  5515.3 1110.57  5558.3 1111.49
  5595.9 1111.66  5606.1 1110.10  5626.9 1110.84  5693.7 1112.98  5752.5 1113.14
#Mann=8,-1,0
  4366.0    0.05       0  5011.4    0.03       0  5015.4    0.05       0
  5106.5    0.12       0  5331.6    0.05       0  5558.3    0.12       0
  5626.9    0.05       0  5693.7    0.12       0
Bank Sta=5011.4,5015.4
Exp/Cntr=0.3,0.1

Type RM Length L Ch R = 1,18227,522,522,522
BEGIN DESCRIPTION:
Mapping XS 07c300dc
END DESCRIPTION:
XS GIS Cut Line= 4
      2917310.43     10156485.09      2918136.85     10156637.87
      2918414.62     10156623.98      2918747.94     10156339.28
#Sta/Elev= 30
  3707.5 1133.78  3804.4 1130.11  3832.0 1128.03  3855.2 1128.35  3884.9 1126.42
  3890.0 1127.84  3895.9 1126.23  3942.9 1122.46  3948.0 1123.59  3995.8 1120.55
  4053.8 1119.99  4068.8 1118.25  4106.8 1119.28  4111.9 1117.84  4150.1 1118.27
  4516.2 1112.06  4586.8 1108.94  4707.0 1109.47  4742.7 1108.85  4747.7 1107.70
  4807.1 1108.51  4899.9 1104.87  4969.6 1102.85  4996.1 1100.76  4996.4 1100.26
  5000.1 1100.76  5132.1 1107.18  5154.0 1107.25  5160.6 1108.81  5264.4 1111.60
#Mann=4,-1,0
  3707.5    0.05       0  4899.9    0.12       0  4996.1    0.07       0
  5000.1    0.12       0
Bank Sta=4996.1,5000.1
Exp/Cntr=0.3,0.1

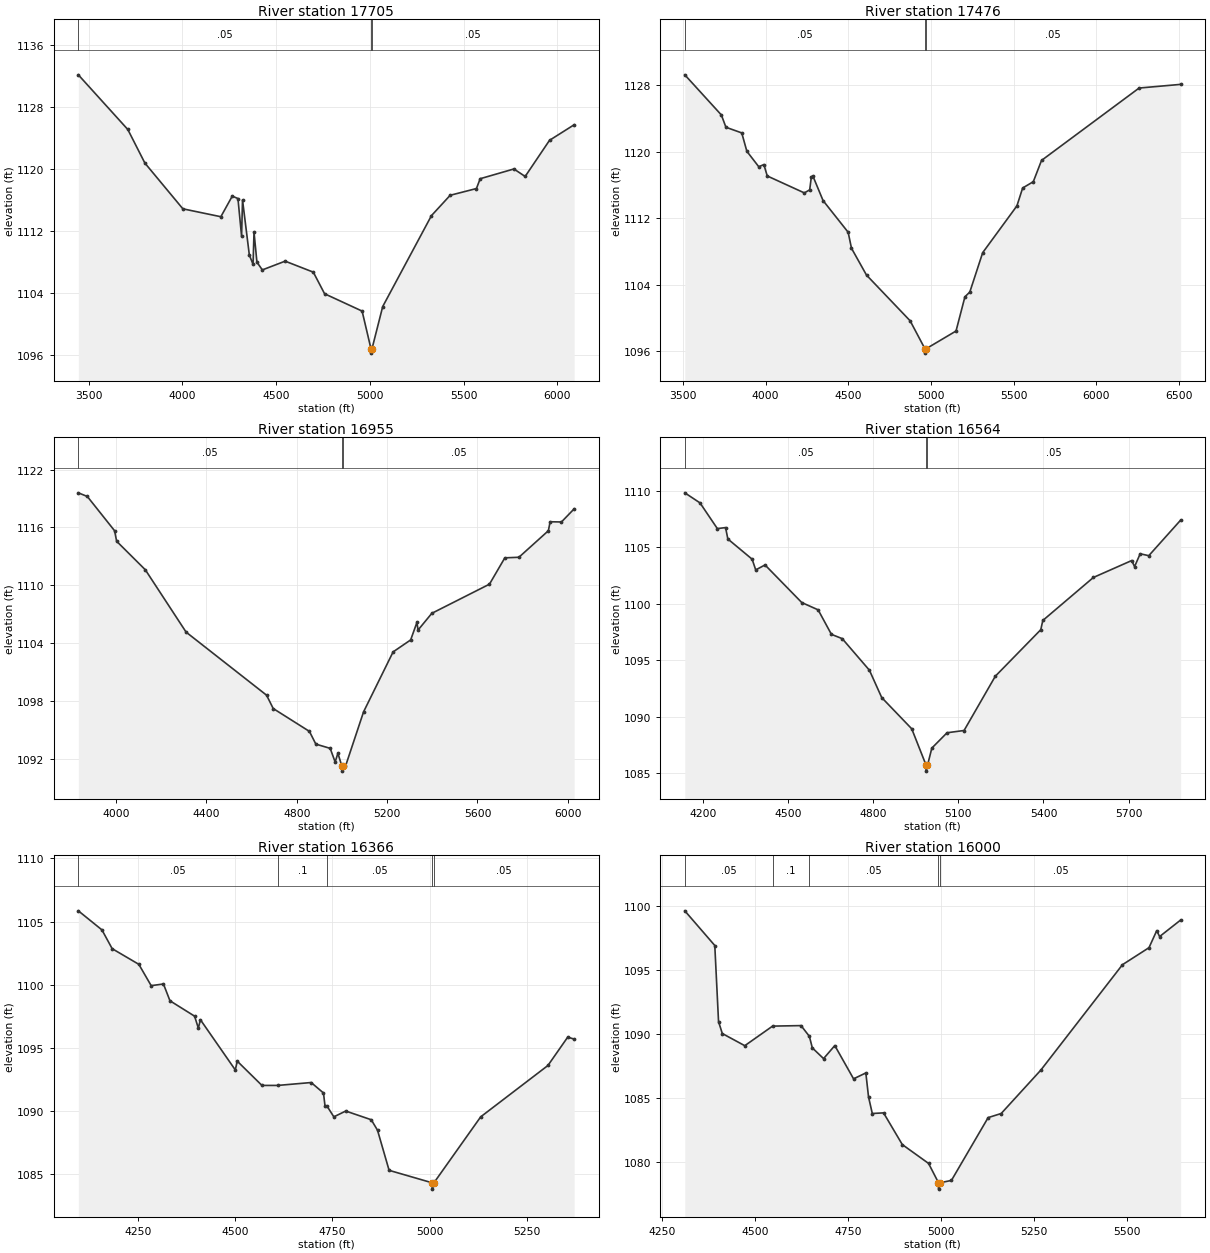
Type RM Length L Ch R = 1,17705,229,229,229
BEGIN DESCRIPTION:
Mapping XS 4a791541
END DESCRIPTION:
XS GIS Cut Line= 4
      2917345.17     10156596.20      2918317.40     10156755.93
      2918789.62     10156783.70      2919977.14     10156804.54
#Sta/Elev= 30
  3444.5 1132.17  3708.5 1125.11  3799.7 1120.77  4002.4 1114.86  4205.1 1113.84
  4265.9 1116.50  4296.3 1116.19  4315.7 1111.32  4320.7 1116.01  4357.1 1108.89
  4376.9 1107.69  4382.0 1111.85  4397.6 1107.97  4426.4 1106.97  4548.2 1108.10
  4698.5 1106.68  4758.6 1103.89  4958.9 1101.65  5006.8 1096.72  5007.0 1096.22
  5011.0 1096.72  5068.9 1102.24  5328.9 1113.98  5428.9 1116.61  5569.0 1117.48
  5589.0 1118.75  5769.0 1120.01  5829.0 1119.04  5959.0 1123.71  6090.5 1125.72
#Mann=3,-1,0
  3444.5    0.05       0  5006.8    0.05       0  5011.0    0.05       0
Bank Sta=5006.8,5011
Exp/Cntr=0.3,0.1

Type RM Length L Ch R = 1,17476,521,521,521
BEGIN DESCRIPTION:
Mapping XS 56c2340c
END DESCRIPTION:
XS GIS Cut Line= 6
      2917460.59     10156700.17      2918172.48     10156869.39
      2918779.33     10156956.92      2919257.80     10157149.47
      2920115.55     10157382.87      2920360.61     10157423.72
#Sta/Elev= 30
  3511.9 1129.27  3733.0 1124.44  3760.6 1122.96  3856.3 1122.28  3887.1 1120.07
  3959.1 1118.21  3990.0 1118.47  4010.5 1117.10  4234.8 1115.06  4267.1 1115.43
  4277.2 1117.01  4287.3 1117.05  4347.9 1114.14  4499.5 1110.33  4519.8 1108.40
  4610.6 1105.17  4874.4 1099.67  4964.5 1096.28  4964.7 1095.78  4968.7 1096.28
  5151.9 1098.44  5205.7 1102.56  5235.2 1103.13  5313.1 1107.87  5520.1 1113.50
  5554.7 1115.65  5619.1 1116.41  5668.9 1118.97  6258.9 1127.68  6509.9 1128.12
#Mann=3,-1,0
  3511.9    0.05       0  4964.5    0.05       0  4968.7    0.05       0
Bank Sta=4964.5,4968.7
Exp/Cntr=0.3,0.1

Type RM Length L Ch R = 1,16955,391,391,391
BEGIN DESCRIPTION:
Mapping XS 975758bc
END DESCRIPTION:
XS GIS Cut Line= 5
      2917732.57     10157086.21      2918339.25     10157276.44
      2918799.38     10157487.22      2919264.64     10157623.46
      2919831.75     10157667.08
#Sta/Elev= 30
  3832.7 1119.59  3872.6 1119.21  3993.2 1115.66  4002.3 1114.57  4129.4 1111.61
  4309.9 1105.15  4666.3 1098.61  4695.6 1097.23  4855.9 1094.86  4884.4 1093.54
  4947.9 1093.10  4969.8 1091.69  4982.1 1092.59  4999.9 1091.24  5000.2 1090.74
  5004.2 1091.24  5015.5 1091.24  5095.8 1096.89  5226.5 1103.10  5304.2 1104.34
  5331.9 1106.15  5337.1 1105.37  5398.0 1107.10  5653.2 1110.12  5721.2 1112.85
  5783.6 1112.91  5914.0 1115.66  5921.8 1116.59  5972.0 1116.57  6028.2 1117.93
#Mann=3,-1,0
  3832.7    0.05       0  4999.9    0.05       0  5004.2    0.05       0
Bank Sta=4999.9,5004.2
Exp/Cntr=0.3,0.1

Type RM Length L Ch R = 1,16564,198,198,198
BEGIN DESCRIPTION:
Mapping XS 8578a526
END DESCRIPTION:
XS GIS Cut Line= 5
      2917786.61     10157471.81      2918269.85     10157682.58
      2918593.73     10157800.83      2918989.59     10157787.97
      2919467.69     10157816.25
#Sta/Elev= 30
  4136.2 1109.84  4189.7 1108.95  4250.9 1106.67  4279.8 1106.76  4287.9 1105.75
  4373.4 1103.96  4386.1 1103.01  4418.9 1103.45  4548.2 1100.12  4606.0 1099.47
  4652.8 1097.30  4690.9 1096.92  4786.7 1094.12  4830.0 1091.70  4935.8 1088.93
  4986.8 1085.68  4987.1 1085.18  4991.2 1085.68  5006.6 1087.22  5060.2 1088.58
  5120.2 1088.78  5230.3 1093.59  5390.4 1097.71  5397.7 1098.53  5575.8 1102.34
  5710.9 1103.84  5720.9 1103.30  5740.7 1104.44  5771.0 1104.27  5883.2 1107.42
#Mann=3,-1,0
  4136.2    0.05       0  4986.8    0.05       0  4991.2    0.05       0
Bank Sta=4986.8,4991.2
Exp/Cntr=0.3,0.1

Type RM Length L Ch R = 1,16366,366,366,366
BEGIN DESCRIPTION:
Mapping XS fd62c6a8
END DESCRIPTION:
XS GIS Cut Line= 3
      2917692.35     10157839.24      2918296.57     10158040.65
      2918921.10     10157915.74
#Sta/Elev= 30
  4097.6 1105.85  4158.2 1104.34  4184.5 1102.85  4253.0 1101.61  4284.7 1099.92
  4316.3 1100.05  4333.0 1098.72  4396.3 1097.50  4405.9 1096.55  4411.2 1097.22
  4500.8 1093.24  4506.0 1093.93  4569.3 1092.01  4609.9 1092.01  4695.8 1092.24
  4727.4 1091.41  4731.4 1090.37  4736.9 1090.35  4754.0 1089.52  4784.6 1089.98
  4850.1 1089.29  4866.2 1088.46  4896.0 1085.28  5006.7 1084.29  5007.0 1083.79
  5011.1 1084.29  5131.3 1089.52  5304.0 1093.59  5354.9 1095.84  5371.4 1095.68
#Mann=5,-1,0
  4097.6    0.05       0  4609.9     0.1       0  4736.9    0.05       0
  5006.7    0.05       0  5011.1    0.05       0
Bank Sta=5006.7,5011.1
Exp/Cntr=0.3,0.1

Type RM Length L Ch R = 1,16000,500,500,500
BEGIN DESCRIPTION:
HORSESHOE CREEK 32.0
END DESCRIPTION:
XS GIS Cut Line= 3
      2917955.70     10158253.11      2918637.98     10158345.41
      2919055.67     10157853.13
#Sta/Elev= 30
  4311.5 1099.61  4392.2 1096.90  4402.3 1090.95  4412.4 1090.02  4472.9 1089.07
  4547.7 1090.60  4624.3 1090.64  4646.7 1089.80  4654.6 1088.90  4684.9 1088.06
  4715.1 1089.08  4765.6 1086.48  4798.6 1086.94  4805.9 1085.06  4816.0 1083.77
  4846.3 1083.82  4896.8 1081.34  4967.4 1079.87  4994.1 1078.36  4994.4 1077.86
  4998.6 1078.36  5028.9 1078.54  5127.7 1083.45  5162.8 1083.77  5269.4 1087.16
  5489.1 1095.40  5560.5 1096.73  5581.3 1098.06  5589.1 1097.60  5645.6 1098.89
#Mann=5,-1,0
  4311.5    0.05       0  4547.7     0.1       0  4646.7    0.05       0
  4994.1    0.05       0  4998.6    0.05       0
Bank Sta=4994.1,4998.6
Exp/Cntr=0.3,0.1

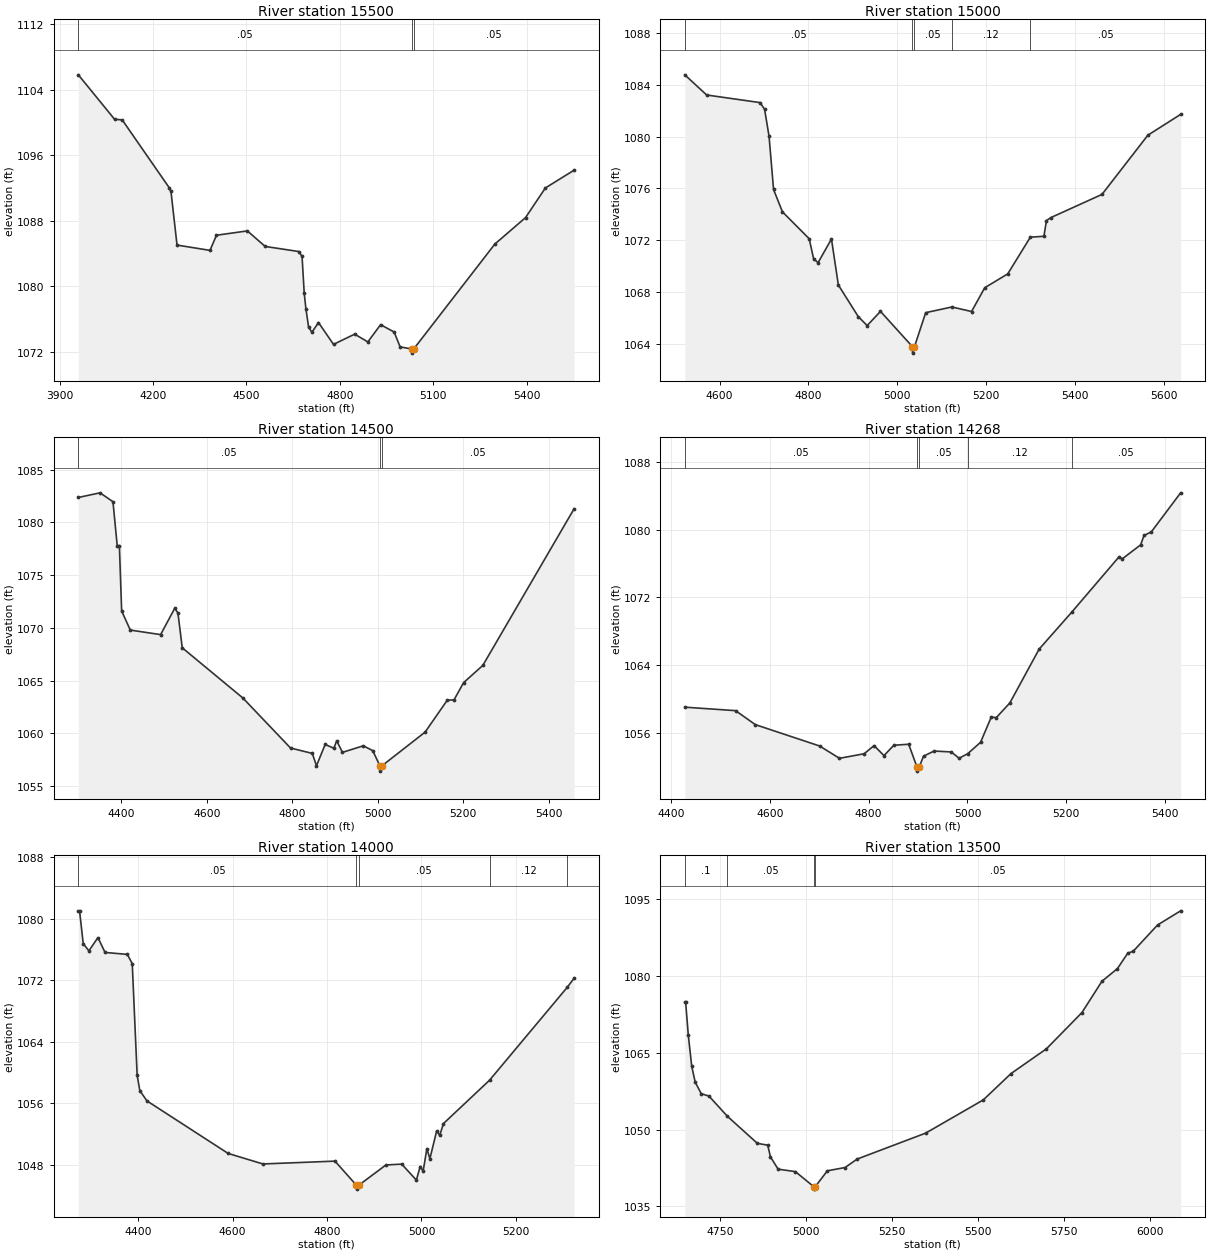
Type RM Length L Ch R = 1,15500,500,500,500
BEGIN DESCRIPTION:
HORSESHOE CREEK 31.0
END DESCRIPTION:
XS GIS Cut Line= 3
      2917755.66     10159153.12      2918739.98     10158817.06
      2919155.67     10158453.12
#Sta/Elev= 30
  3959.9 1105.84  4076.2 1100.41  4100.9 1100.33  4252.2 1092.02  4257.5 1091.58
  4276.9 1085.03  4382.8 1084.38  4403.6 1086.23  4502.8 1086.76  4560.2 1084.86
  4667.9 1084.24  4678.5 1083.64  4685.5 1079.12  4690.8 1077.27  4699.6 1074.99
  4710.2 1074.37  4731.3 1075.56  4779.5 1072.89  4847.5 1074.14  4889.8 1073.19
  4930.8 1075.30  4974.3 1074.40  4993.5 1072.58  5032.5 1072.32  5032.8 1071.82
  5037.0 1072.32  5297.7 1085.15  5396.4 1088.39  5460.0 1092.01  5552.5 1094.19
#Mann=3,-1,0
  3959.9    0.05       0  5032.5    0.05       0  5037.0    0.05       0
Bank Sta=5032.5,5037
Exp/Cntr=0.3,0.1

Type RM Length L Ch R = 1,15000,500,500,500
BEGIN DESCRIPTION:
HORSESHOE CREEK 30.0
END DESCRIPTION:
XS GIS Cut Line= 3
      2918256.60     10159314.25      2918733.43     10159278.12
      2919291.74     10158970.60
#Sta/Elev= 30
  4521.8 1084.79  4571.0 1083.23  4691.4 1082.64  4701.4 1082.11  4711.4 1080.03
  4721.5 1075.92  4741.5 1074.19  4801.7 1072.11  4811.7 1070.55  4821.7 1070.26
  4851.8 1072.09  4867.3 1068.53  4912.0 1066.09  4932.1 1065.39  4962.1 1066.49
  5034.0 1063.76  5034.3 1063.26  5038.6 1063.76  5063.8 1066.39  5122.7 1066.83
  5167.0 1066.48  5196.7 1068.32  5248.4 1069.39  5299.3 1072.23  5329.8 1072.30
  5335.5 1073.51  5345.1 1073.74  5460.5 1075.54  5563.7 1080.12  5637.4 1081.73
#Mann=5,-1,0
  4521.8    0.05       0  5034.0    0.03       0  5038.6    0.05       0
  5122.7    0.12       0  5299.3    0.05       0
Bank Sta=5034,5038.6
Exp/Cntr=0.3,0.1

Type RM Length L Ch R = 1,14500,232,232,232
BEGIN DESCRIPTION:
HORSESHOE CREEK 29.0
END DESCRIPTION:
XS GIS Cut Line= 3
      2918355.65     10159553.11      2919047.29     10159662.92
      2919455.65     10159453.13
#Sta/Elev= 30
  4299.7 1082.37  4350.4 1082.81  4380.7 1081.97  4390.6 1077.81  4395.7 1077.80
  4401.0 1071.61  4421.2 1069.80  4492.1 1069.37  4525.2 1071.87  4532.6 1071.42
  4542.7 1068.12  4684.5 1063.36  4795.9 1058.62  4846.7 1058.11  4856.6 1056.94
  4876.9 1058.96  4897.1 1058.60  4903.9 1059.30  4917.4 1058.21  4966.1 1058.83
  4988.2 1058.37  5004.8 1056.93  5005.2 1056.43  5009.5 1056.93  5110.6 1060.13
  5162.5 1063.16  5178.1 1063.18  5200.6 1064.82  5245.5 1066.45  5459.1 1081.31
#Mann=3,-1,0
  4299.7    0.05       0  5004.8    0.05       0  5009.5    0.05       0
Bank Sta=5004.8,5009.5
Exp/Cntr=0.3,0.1

Type RM Length L Ch R = 1,14268,268,268,268
BEGIN DESCRIPTION:
Mapping XS 861f5d0d
END DESCRIPTION:
XS GIS Cut Line= 3
      2918622.96     10159894.82      2919116.01     10159887.87
      2919560.25     10159637.99
#Sta/Elev= 30
  4428.3 1059.06  4531.0 1058.65  4571.0 1057.00  4701.1 1054.48  4741.1 1053.03
  4791.1 1053.57  4811.1 1054.53  4831.1 1053.35  4851.1 1054.57  4881.1 1054.69
  4897.8 1052.02  4898.2 1051.52  4902.5 1052.02  4911.1 1053.28  4932.5 1053.89
  4967.2 1053.78  4983.1 1053.04  5000.6 1053.58  5026.5 1054.92  5048.1 1057.89
  5058.3 1057.83  5085.7 1059.56  5145.0 1065.91  5210.6 1070.24  5306.9 1076.81
  5312.7 1076.53  5350.3 1078.20  5357.0 1079.30  5371.9 1079.73  5431.1 1084.33
#Mann=5,-1,0
  4428.3    0.05       0  4897.8    0.05       0  4902.5    0.05       0
  5000.6    0.12       0  5210.6    0.05       0
Bank Sta=4897.8,4902.5
Exp/Cntr=0.3,0.1

Type RM Length L Ch R = 1,14000,500,500,500
BEGIN DESCRIPTION:
HORSESHOE CREEK 28.0
END DESCRIPTION:
XS GIS Cut Line= 3
      2918455.65     10160303.12      2919156.09     10160108.77
      2919405.68     10159903.12
#Sta/Elev= 30
  4273.1 1081.00  4275.7 1081.00  4283.5 1076.73  4295.5 1075.80  4314.6 1077.52
  4329.7 1075.59  4376.9 1075.34  4387.3 1074.14  4397.7 1059.61  4403.4 1057.63
  4418.4 1056.30  4590.4 1049.47  4664.1 1048.10  4816.7 1048.47  4862.3 1045.33
  4862.6 1044.83  4867.0 1045.33  4924.7 1047.97  4958.1 1048.08  4989.2 1046.00
  4997.2 1047.77  5003.5 1047.16  5011.4 1050.10  5017.8 1048.78  5032.2 1052.41
  5038.7 1051.82  5046.5 1053.35  5144.1 1058.98  5308.9 1071.07  5323.4 1072.25
#Mann=5,-1,0
  4273.1    0.05       0  4862.3    0.05       0  4867.0    0.05       0
  5144.1    0.12       0  5308.9    0.05       0
Bank Sta=4862.3,4867
Exp/Cntr=0.3,0.1

Type RM Length L Ch R = 1,13500,210,210,210
BEGIN DESCRIPTION:
HORSESHOE CREEK 27.0
END DESCRIPTION:
XS GIS Cut Line= 3
      2918555.66     10160503.11      2918907.71     10160538.20
      2919855.72     10160003.09
#Sta/Elev= 30
  4646.2 1074.85  4648.7 1074.85  4656.3 1068.52  4666.3 1062.39  4676.4 1059.29
  4694.0 1057.03  4716.6 1056.55  4770.3 1052.60  4857.3 1047.33  4887.4 1046.97
  4895.4 1044.69  4917.6 1042.29  4967.8 1041.81  5021.1 1038.89  5021.4 1038.39
  5025.9 1038.89  5061.0 1041.97  5112.5 1042.61  5147.6 1044.26  5347.0 1049.33
  5514.5 1055.81  5595.3 1060.96  5698.1 1065.78  5801.5 1072.86  5859.6 1078.97
  5904.8 1081.45  5934.8 1084.46  5950.7 1084.84  6021.4 1089.96  6088.6 1092.73
#Mann=4,-1,0
  4646.2     0.1       0  4770.3    0.05       0  5021.1    0.03       0
  5025.9    0.05       0
Bank Sta=5021.1,5025.9
Exp/Cntr=0.3,0.1