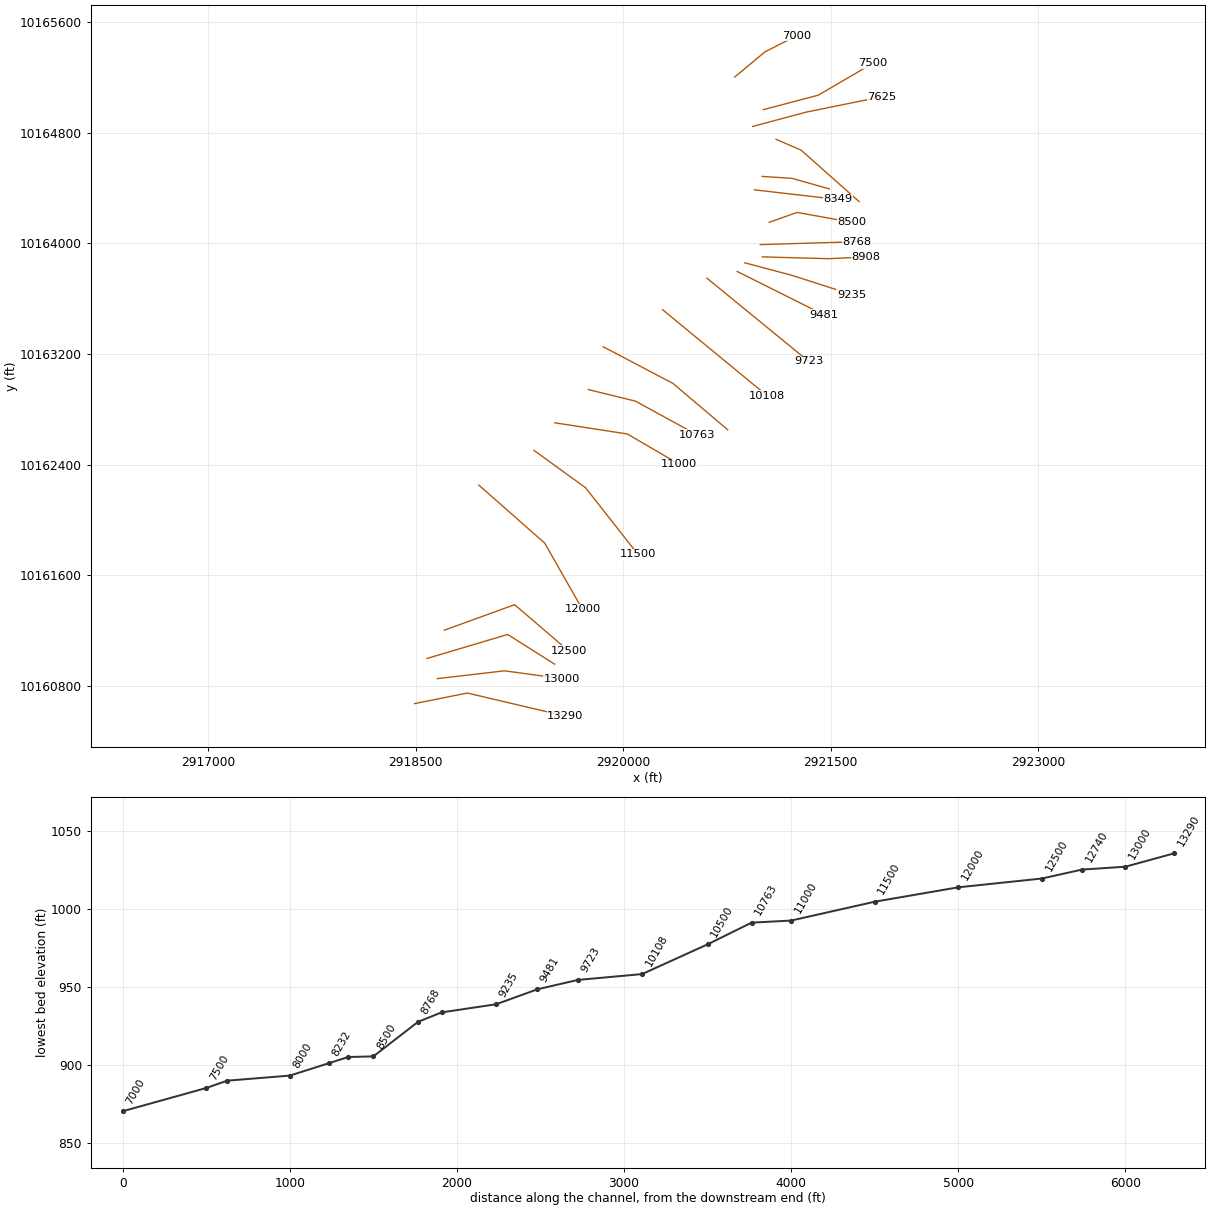
HEC-RAS study HORSESHOE CREEK.prj: HORSESHOE CREEK Base Level Engineering

--- HORSESHOE CREEK.g01 (geometry) --- (continued)

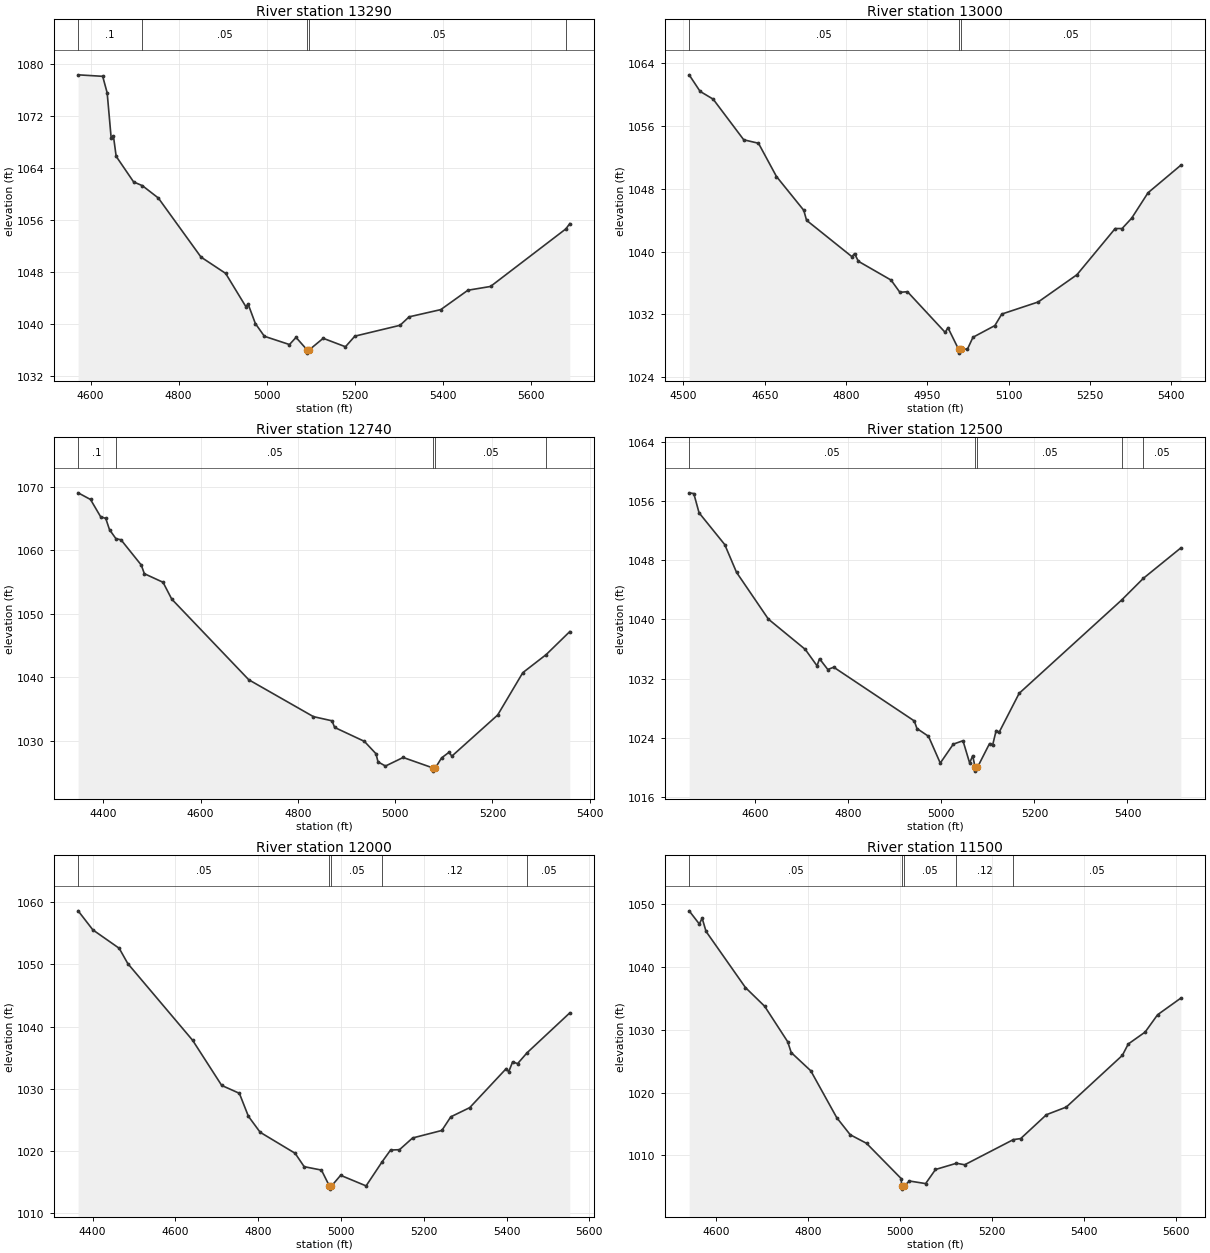
Type RM Length L Ch R = 1,13290,290,290,290
BEGIN DESCRIPTION:
Mapping XS 19063be2
END DESCRIPTION:
XS GIS Cut Line= 3
      2918491.00     10160672.59      2918872.96     10160748.98
      2919581.00     10160582.38
#Sta/Elev= 30
  4571.7 1078.36  4627.5 1078.13  4637.7 1075.58  4646.8 1068.61  4651.9 1068.96
  4658.1 1065.83  4697.8 1061.89  4717.6 1061.32  4753.9 1059.42  4850.8 1050.34
  4906.8 1047.83  4952.7 1042.72  4957.8 1043.12  4974.3 1040.12  4994.8 1038.16
  5051.8 1036.89  5066.7 1037.99  5091.8 1036.07  5092.2 1035.57  5096.6 1036.07
  5128.4 1037.85  5179.0 1036.55  5200.3 1038.18  5303.0 1039.85  5323.6 1041.15
  5395.5 1042.26  5457.1 1045.24  5508.5 1045.82  5679.6 1054.67  5688.6 1055.49
#Mann=5,-1,0
  4571.7     0.1       0  4717.6    0.05       0  5091.8    0.05       0
  5096.6    0.05       0  5679.6    0.12       0
Bank Sta=5091.8,5096.6
Exp/Cntr=0.3,0.1

Type RM Length L Ch R = 1,13000,260,260,260
BEGIN DESCRIPTION:
HORSESHOE CREEK 26.0
END DESCRIPTION:
XS GIS Cut Line= 3
      2918655.65     10160853.11      2919141.88     10160909.60
      2919555.64     10160853.12
#Sta/Elev= 30
  4510.5 1062.53  4530.7 1060.42  4554.8 1059.43  4611.2 1054.25  4638.4 1053.81
  4671.6 1049.57  4722.0 1045.26  4727.1 1043.99  4810.7 1039.36  4815.7 1039.75
  4822.6 1038.77  4883.0 1036.37  4899.3 1034.81  4913.2 1034.89  4982.9 1029.70
  4987.9 1030.31  5007.5 1027.56  5007.9 1027.06  5012.4 1027.56  5024.0 1027.58
  5034.1 1029.08  5074.5 1030.57  5087.3 1032.04  5154.5 1033.58  5225.9 1037.05
  5296.5 1042.94  5309.2 1042.94  5326.8 1044.25  5357.1 1047.50  5417.6 1051.01
#Mann=3,-1,0
  4510.5    0.05       0  5007.5    0.05       0  5012.4    0.05       0
Bank Sta=5007.5,5012.4
Exp/Cntr=0.3,0.1

Type RM Length L Ch R = 1,12740,240,240,240
BEGIN DESCRIPTION:
Mapping XS f6e19347
END DESCRIPTION:
XS GIS Cut Line= 3
      2918581.26     10160998.97      2919164.62     10161172.59
      2919504.30     10160957.69
#Sta/Elev= 30
  4348.4 1069.02  4373.9 1067.97  4394.7 1065.25  4405.2 1064.99  4412.9 1063.22
  4426.2 1061.79  4436.5 1061.63  4478.2 1057.65  4484.5 1056.29  4522.9 1054.94
  4540.8 1052.29  4699.2 1039.59  4832.0 1033.79  4870.3 1033.13  4875.6 1032.09
  4936.7 1029.90  4960.6 1027.95  4964.8 1026.67  4980.1 1026.01  5016.5 1027.36
  5077.7 1025.71  5078.0 1025.21  5082.6 1025.71  5095.4 1027.29  5110.6 1028.17
  5116.6 1027.57  5210.7 1034.04  5262.4 1040.71  5310.5 1043.56  5359.0 1047.18
#Mann=5,-1,0
  4348.4     0.1       0  4426.2    0.05       0  5077.7    0.05       0
  5082.6    0.05       0  5310.5    0.12       0
Bank Sta=5077.7,5082.6
Exp/Cntr=0.3,0.1

Type RM Length L Ch R = 1,12500,500,500,500
BEGIN DESCRIPTION:
HORSESHOE CREEK 25.0
END DESCRIPTION:
XS GIS Cut Line= 3
      2918705.65     10161203.10      2919214.89     10161388.09
      2919605.67     10161053.12
#Sta/Elev= 30
  4458.2 1057.12  4468.2 1057.02  4479.5 1054.42  4534.7 1050.12  4560.0 1046.37
  4628.5 1040.04  4707.7 1035.95  4733.0 1033.73  4738.3 1034.69  4756.1 1033.23
  4768.9 1033.54  4941.9 1026.28  4947.7 1025.25  4972.5 1024.20  4997.8 1020.58
  5025.8 1023.14  5046.6 1023.60  5060.9 1020.59  5067.5 1021.58  5072.7 1019.99
  5073.0 1019.49  5077.6 1019.99  5103.7 1023.22  5110.3 1023.01  5117.9 1024.98
  5124.5 1024.77  5167.3 1030.01  5387.4 1042.62  5434.2 1045.56  5514.7 1049.67
#Mann=5,-1,0
  4458.2    0.05       0  5072.7    0.03       0  5077.6    0.05       0
  5387.4    0.12       0  5434.2    0.05       0
Bank Sta=5072.7,5077.6
Exp/Cntr=0.3,0.1

Type RM Length L Ch R = 1,12000,500,500,500
BEGIN DESCRIPTION:
HORSESHOE CREEK 24.0
END DESCRIPTION:
XS GIS Cut Line= 3
      2918955.67     10162253.13      2919432.20     10161833.29
      2919705.69     10161353.11
#Sta/Elev= 30
  4364.9 1058.60  4400.5 1055.54  4464.1 1052.58  4485.0 1050.11  4641.5 1037.79
  4711.7 1030.54  4754.4 1029.27  4776.2 1025.58  4804.6 1023.01  4889.1 1019.63
  4910.9 1017.48  4952.7 1016.93  4971.9 1014.37  4972.3 1013.87  4976.9 1014.37
  4999.0 1016.09  5060.5 1014.39  5099.5 1018.29  5119.6 1020.15  5141.2 1020.21
  5172.8 1022.09  5243.5 1023.30  5265.1 1025.49  5310.9 1026.97  5399.1 1033.25
  5404.9 1032.71  5414.5 1034.33  5426.5 1034.04  5449.4 1035.79  5552.6 1042.20
#Mann=5,-1,0
  4364.9    0.05       0  4971.9    0.03       0  4976.9    0.05       0
  5099.5    0.12       0  5449.4    0.05       0
Bank Sta=4971.9,4976.9
Exp/Cntr=0.3,0.1

Type RM Length L Ch R = 1,11500,500,500,500
BEGIN DESCRIPTION:
HORSESHOE CREEK 23.0
END DESCRIPTION:
XS GIS Cut Line= 3
      2919355.65     10162503.13      2919727.70     10162233.81
      2920105.68     10161753.12
#Sta/Elev= 30
  4540.7 1048.87  4562.8 1046.78  4569.0 1047.70  4577.5 1045.60  4663.3 1036.68
  4705.1 1033.71  4755.3 1028.07  4763.0 1026.35  4805.6 1023.45  4862.1 1016.01
  4891.5 1013.29  4927.0 1011.93  5002.4 1006.33  5003.5 1005.15  5003.9 1004.65
  5008.6 1005.15  5020.5 1005.94  5055.7 1005.53  5077.2 1007.77  5122.9 1008.76
  5140.8 1008.52  5246.8 1012.52  5262.7 1012.68  5318.9 1016.48  5362.1 1017.69
  5484.1 1025.90  5497.0 1027.71  5533.8 1029.61  5560.9 1032.36  5611.5 1035.00
#Mann=5,-1,0
  4540.7    0.05       0  5003.5    0.03       0  5008.6    0.05       0
  5122.9    0.12       0  5246.8    0.05       0
Bank Sta=5003.5,5008.6
Exp/Cntr=0.3,0.1

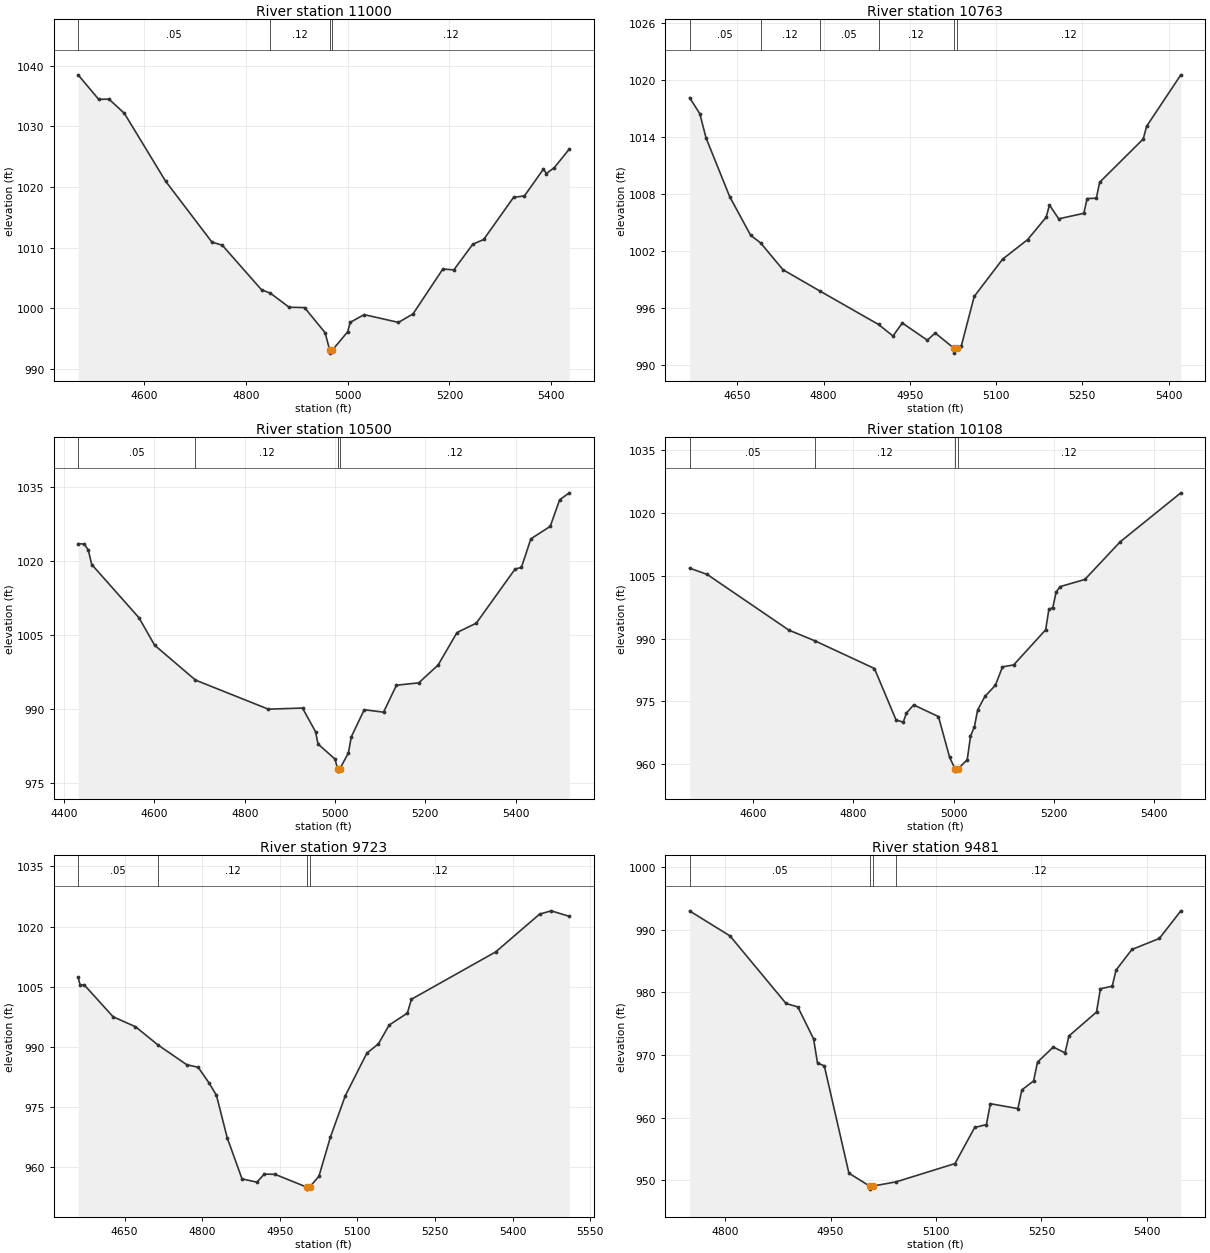
Type RM Length L Ch R = 1,11000,237,237,237
BEGIN DESCRIPTION:
HORSESHOE CREEK 22.0
END DESCRIPTION:
XS GIS Cut Line= 3
      2919505.71     10162703.11      2920029.45     10162622.58
      2920405.71     10162403.09
#Sta/Elev= 30
  4470.1 1038.50  4510.5 1034.46  4530.8 1034.49  4561.1 1032.14  4642.1 1020.95
  4733.1 1010.91  4753.4 1010.40  4830.6 1003.04  4848.0 1002.48  4884.9 1000.16
  4915.2 1000.10  4955.7  995.95  4964.6  993.09  4965.0  992.59  4969.9  993.09
  5000.0  996.12  5005.1  997.68  5032.4  998.94  5099.8  997.66  5128.4  999.06
  5187.1 1006.47  5208.6 1006.32  5245.8 1010.55  5267.3 1011.34  5326.0 1018.28
  5347.5 1018.54  5384.7 1022.95  5390.5 1022.22  5406.2 1023.20  5435.6 1026.26
#Mann=4,-1,0
  4470.1    0.05       0  4848.0    0.12       0  4964.6    0.07       0
  4969.9    0.12       0
Bank Sta=4964.6,4969.9
Exp/Cntr=0.3,0.1

Type RM Length L Ch R = 1,10763,263,263,263
BEGIN DESCRIPTION:
Mapping XS fd331706
END DESCRIPTION:
XS GIS Cut Line= 3
      2919747.96     10162943.42      2920088.23     10162860.09
      2920530.67     10162618.14
#Sta/Elev= 30
  4566.8 1018.11  4584.5 1016.42  4595.3 1013.88  4636.5 1007.70  4672.9 1003.64
  4690.1 1002.85  4729.2 1000.02  4792.8  997.80  4895.5  994.26  4920.6  993.05
  4936.7  994.42  4980.3  992.61  4994.0  993.37  5027.0  991.75  5027.4  991.25
  5032.3  991.75  5039.6  992.04  5061.9  997.21  5111.3 1001.13  5154.9 1003.19
  5187.1 1005.54  5192.8 1006.83  5208.9 1005.37  5252.6 1005.95  5258.3 1007.50
  5274.4 1007.54  5280.1 1009.21  5356.0 1013.77  5361.7 1015.09  5421.4 1020.51
#Mann=6,-1,0
  4566.8    0.05       0  4690.1    0.12       0  4792.8    0.05       0
  4895.5    0.12       0  5027.0    0.07       0  5032.3    0.12       0
Bank Sta=5027,5032.3
Exp/Cntr=0.3,0.1

Type RM Length L Ch R = 1,10500,392,392,392
BEGIN DESCRIPTION:
HORSESHOE CREEK 21.0
END DESCRIPTION:
XS GIS Cut Line= 3
      2919855.69     10163253.11      2920359.47     10162988.16
      2920755.69     10162653.11
#Sta/Elev= 30
  4430.8 1023.52  4444.6 1023.46  4453.4 1022.21  4461.0 1019.30  4565.6 1008.50
  4600.3 1002.92  4690.8  995.84  4852.1  989.94  4927.9  990.16  4956.7  985.37
  4962.3  982.86  5000.0  979.80  5005.4  977.86  5005.9  977.36  5010.8  977.86
  5029.4  981.02  5036.0  984.33  5064.6  989.82  5107.4  989.33  5136.0  994.80
  5185.4  995.28  5228.3  998.90  5270.1 1005.49  5312.9 1007.40  5398.6 1018.36
  5412.9 1018.73  5433.7 1024.51  5476.6 1027.04  5497.5 1032.44  5518.9 1033.85
#Mann=4,-1,0
  4430.8    0.05       0  4690.8    0.12       0  5005.4    0.07       0
  5010.8    0.12       0
Bank Sta=5005.4,5010.8
Exp/Cntr=0.3,0.1

Type RM Length L Ch R = 1,10108,385,385,385
BEGIN DESCRIPTION:
Mapping XS be52d07b
END DESCRIPTION:
XS GIS Cut Line= 2
      2920284.78     10163521.33      2921041.29     10162898.67
#Sta/Elev= 30
  4473.3 1006.81  4508.3 1005.31  4671.2  992.01  4723.6  989.43  4841.9  982.84
  4885.0  970.56  4899.3  970.03  4905.8  972.20  4920.1  974.15  4969.6  971.36
  4991.9  961.62  5002.8  958.83  5003.2  958.33  5008.2  958.83  5027.0  961.05
  5033.5  966.64  5041.4  968.97  5047.8  972.96  5062.2  976.16  5083.2  978.85
  5097.3  983.23  5119.6  983.70  5183.4  992.08  5189.9  997.00  5197.7  997.39
  5204.2 1001.05  5212.1 1002.39  5261.6 1004.11  5331.9 1013.08  5453.1 1024.80
#Mann=4,-1,0
  4473.3    0.05       0  4723.6    0.12       0  5002.8    0.07       0
  5008.2    0.12       0
Bank Sta=5002.8,5008.2
Exp/Cntr=0.3,0.1

Type RM Length L Ch R = 1,9723,242,242,242
BEGIN DESCRIPTION:
Mapping XS b8ae9381
END DESCRIPTION:
XS GIS Cut Line= 2
      2920605.70     10163748.90      2921340.68     10163148.08
#Sta/Elev= 30
  4560.2 1007.46  4564.0 1005.45  4571.9 1005.50  4627.9  997.53  4671.0  995.06
  4715.3  990.44  4770.1  985.59  4792.3  984.94  4813.1  981.06  4827.5  977.98
  4848.3  967.40  4877.0  957.12  4905.7  956.31  4920.1  958.33  4940.9  958.25
  5002.1  955.07  5002.5  954.57  5007.6  955.07  5025.6  957.78  5047.9  967.58
  5076.6  977.86  5118.2  988.46  5140.5  990.76  5161.3  995.46  5196.5  998.44
  5204.4 1001.90  5367.3 1013.71  5452.0 1023.11  5474.3 1023.94  5509.5 1022.57
#Mann=4,-1,0
  4560.2    0.05       0  4715.3    0.12       0  5002.1    0.07       0
  5007.6    0.12       0
Bank Sta=5002.1,5007.6
Exp/Cntr=0.3,0.1

Type RM Length L Ch R = 1,9481,246,246,246
BEGIN DESCRIPTION:
Mapping XS accadae6
END DESCRIPTION:
XS GIS Cut Line= 2
      2920824.33     10163797.60      2921449.36     10163485.09
#Sta/Elev= 30
  4749.6  992.96  4807.0  988.98  4886.7  978.20  4903.5  977.64  4925.9  972.55
  4931.5  968.70  4941.2  968.23  4976.2  951.11  5005.5  949.07  5006.0  948.57
  5011.0  949.07  5043.6  949.74  5127.1  952.65  5155.1  958.41  5171.8  958.87
  5177.4  962.20  5216.6  961.42  5222.2  964.40  5238.9  965.84  5244.5  968.84
  5266.9  971.24  5283.6  970.32  5289.2  973.01  5328.4  976.83  5334.0  980.55
  5350.7  980.95  5356.3  983.53  5378.7  986.81  5417.8  988.57  5448.4  992.98
#Mann=4,-1,0
  4749.6    0.05       0  5005.5    0.03       0  5011.0    0.05       0
  5043.6    0.12       0
Bank Sta=5005.5,5011
Exp/Cntr=0.3,0.1

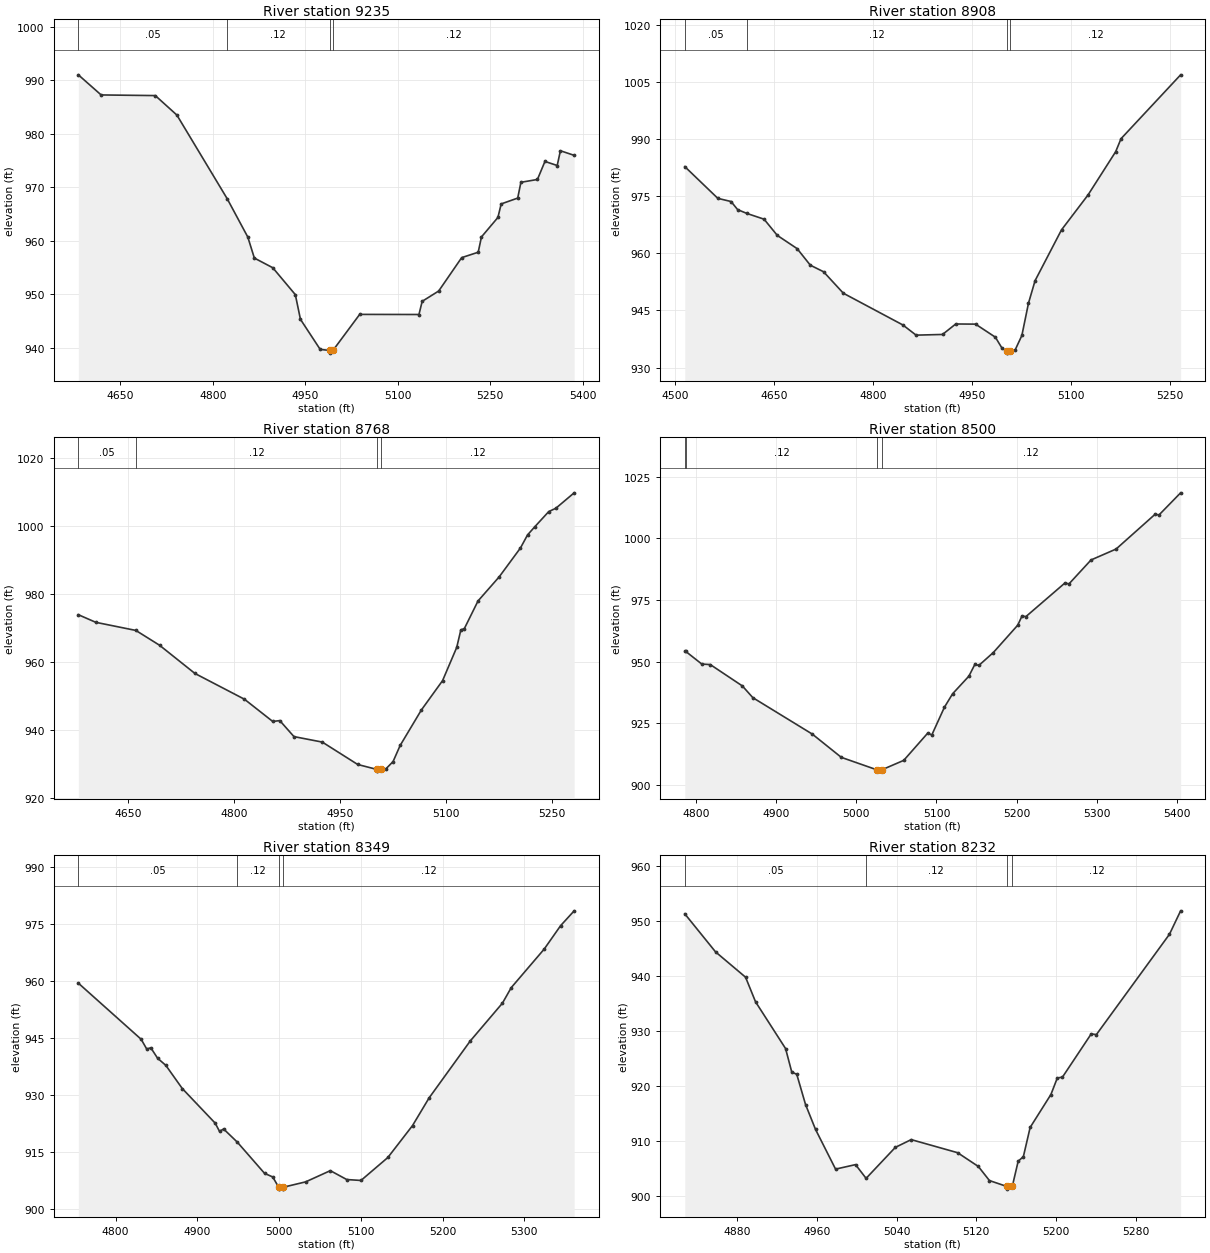
Type RM Length L Ch R = 1,9235,327,327,327
BEGIN DESCRIPTION:
Mapping XS 647d4459
END DESCRIPTION:
XS GIS Cut Line= 3
      2920879.87     10163860.10      2921220.18     10163769.82
      2921650.75     10163630.92
#Sta/Elev= 30
  4581.9  991.04  4618.9  987.28  4706.8  987.16  4741.8  983.52  4823.4  967.89
  4856.9  960.71  4867.5  956.79  4897.4  954.98  4934.0  949.95  4942.3  945.34
  4974.3  939.72  4989.5  939.52  4990.0  939.02  4995.0  939.52  5038.4  946.26
  5134.6  946.24  5139.8  948.70  5166.6  950.63  5203.9  956.87  5230.7  957.88
  5236.0  960.74  5262.7  964.38  5268.0  966.91  5294.8  968.00  5300.0  970.95
  5326.8  971.48  5339.0  974.85  5358.9  974.09  5364.1  976.85  5386.4  975.99
#Mann=4,-1,0
  4581.9    0.05       0  4823.4    0.12       0  4989.5    0.07       0
  4995.0    0.12       0
Bank Sta=4989.5,4995
Exp/Cntr=0.3,0.1

Type RM Length L Ch R = 1,8908,140,140,140
BEGIN DESCRIPTION:
HORSESHOE CREEK 18.0
END DESCRIPTION:
XS GIS Cut Line= 3
      2921005.73     10163903.11      2921490.25     10163890.00
      2921755.73     10163903.11
#Sta/Elev= 30
  4515.3  982.74  4565.3  974.41  4585.3  973.58  4595.3  971.45  4609.3  970.45
  4635.3  968.94  4655.3  964.69  4685.3  961.22  4705.3  956.87  4725.3  955.15
  4755.3  949.51  4845.4  941.18  4865.4  938.51  4905.4  938.69  4925.4  941.44
  4955.4  941.40  4985.4  937.97  4995.2  935.16  5002.6  934.29  5003.1  933.79
  5008.2  934.29  5015.5  934.69  5025.5  938.42  5035.5  946.89  5045.5  952.81
  5085.5  966.14  5125.6  975.29  5167.5  986.66  5175.6  990.07  5265.8 1006.83
#Mann=4,-1,0
  4515.3    0.05       0  4609.3    0.12       0  5002.6    0.07       0
  5008.2    0.12       0
Bank Sta=5002.6,5008.2
Exp/Cntr=0.3,0.1

Type RM Length L Ch R = 1,8768,268,268,268
BEGIN DESCRIPTION:
Mapping XS 62684c62
END DESCRIPTION:
XS GIS Cut Line= 2
      2920990.98     10163992.04      2921691.57     10164012.85
#Sta/Elev= 30
  4579.9  973.88  4604.6  971.64  4661.2  969.25  4694.7  964.89  4744.7  956.58
  4814.7  948.99  4854.7  942.44  4864.7  942.69  4884.7  937.98  4924.8  936.36
  4974.8  929.77  5002.0  928.31  5002.4  927.81  5007.6  928.31  5014.8  928.51
  5024.8  930.62  5034.8  935.36  5064.8  945.81  5094.8  954.47  5114.8  964.25
  5120.6  969.38  5125.6  969.80  5144.9  977.93  5174.9  985.05  5204.9  993.54
  5214.9  997.38  5224.9  999.73  5244.9 1004.26  5254.9 1005.23  5280.8 1009.78
#Mann=4,-1,0
  4579.9    0.05       0  4661.2    0.12       0  5002.0    0.07       0
  5007.6    0.12       0
Bank Sta=5002,5007.6
Exp/Cntr=0.3,0.1

Type RM Length L Ch R = 1,8500,151,151,151
BEGIN DESCRIPTION:
HORSESHOE CREEK 17.0
END DESCRIPTION:
XS GIS Cut Line= 3
      2921055.70     10164153.12      2921257.38     10164224.68
      2921655.70     10164153.11
#Sta/Elev= 30
  4786.0  954.17  4787.1  954.17  4807.2  949.03  4817.8  948.82  4857.8  940.17
  4870.9  935.41  4945.1  920.65  4981.3  911.23  5026.0  906.15  5026.4  905.65
  5031.6  906.15  5059.2  910.01  5089.2  921.07  5094.2  920.28  5110.0  931.56
  5120.2  937.00  5140.5  944.13  5147.9  948.86  5153.0  948.49  5171.0  953.70
  5201.5  964.80  5206.7  968.47  5211.7  968.27  5260.3  981.86  5265.4  981.51
  5292.9  991.20  5324.2  995.63  5372.8 1009.70  5377.8 1009.46  5404.7 1018.40
#Mann=4,-1,0
  4786.0    0.05       0  4787.1    0.12       0  5026.0    0.07       0
  5031.6    0.12       0
Bank Sta=5026,5031.6
Exp/Cntr=0.3,0.1

Type RM Length L Ch R = 1,8349,117,117,117
BEGIN DESCRIPTION:
Mapping XS 8a90f9fc
END DESCRIPTION:
XS GIS Cut Line= 2
      2920949.32     10164387.87      2921552.15     10164318.58
#Sta/Elev= 30
  4754.3  959.42  4831.2  944.65  4838.0  942.09  4843.0  942.42  4851.3  939.67
  4861.4  937.79  4881.5  931.70  4921.8  922.59  4927.1  920.43  4932.1  921.06
  4948.9  917.59  4982.2  909.39  4992.2  908.44  4999.5  905.74  4999.9  905.24
  5004.6  905.24  5005.1  905.74  5032.5  907.15  5062.7  910.10  5082.8  907.76
  5100.2  907.52  5133.1  913.56  5163.3  921.96  5183.5  929.21  5233.8  944.17
  5273.3  954.15  5284.1  958.24  5324.4  968.37  5344.5  974.53  5361.1  978.44
#Mann=4,-1,0
  4754.3    0.05       0  4948.9    0.12       0  4999.5    0.07       0
  5005.1    0.12       0
Bank Sta=4999.5,5005.1
Exp/Cntr=0.3,0.1

Type RM Length L Ch R = 1,8232,232,232,232
BEGIN DESCRIPTION:
Mapping XS d31f8097
END DESCRIPTION:
XS GIS Cut Line= 3
      2921004.91     10164485.09      2921220.18     10164471.20
      2921490.80     10164394.88
#Sta/Elev= 30
  4827.8  951.31  4858.6  944.39  4888.7  939.78  4898.7  935.30  4928.8  926.79
  4935.0  922.51  4940.0  922.11  4948.8  916.61  4958.8  912.08  4978.9  904.85
  4998.9  905.67  5009.5  903.17  5038.8  908.81  5054.7  910.22  5101.2  907.84
  5122.0  905.33  5133.1  902.77  5150.3  901.71  5150.8  901.21  5156.0  901.71
  5161.9  906.29  5167.1  907.12  5173.9  912.44  5194.7  918.43  5201.1  921.43
  5206.3  921.60  5235.1  929.46  5240.3  929.34  5313.5  947.59  5324.7  951.86
#Mann=4,-1,0
  4827.8    0.05       0  5009.5    0.12       0  5150.3    0.03       0
  5156.0    0.12       0
Bank Sta=5150.3,5156
Exp/Cntr=0.3,0.1

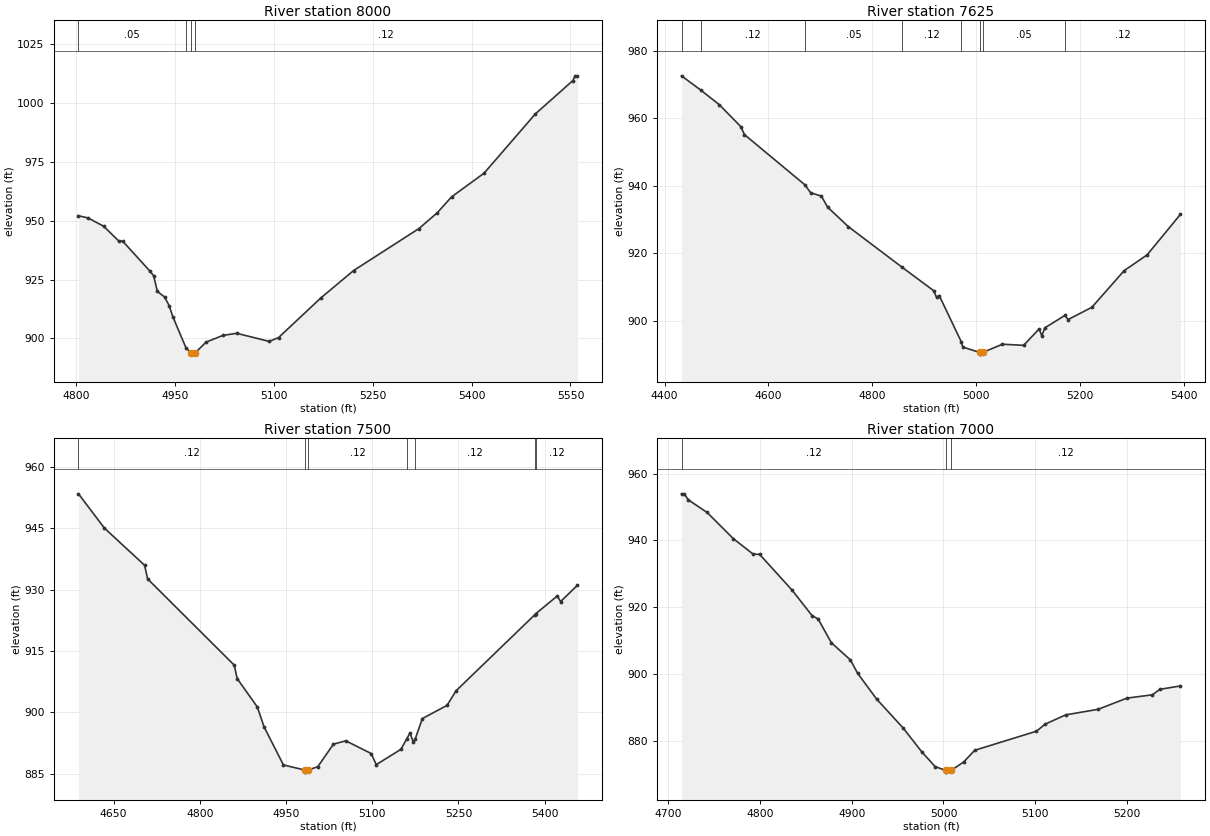
Type RM Length L Ch R = 1,8000,375,375,375
BEGIN DESCRIPTION:
HORSESHOE CREEK 16.0
END DESCRIPTION:
XS GIS Cut Line= 3
      2921105.69     10164753.11      2921286.48     10164675.36
      2921705.66     10164303.13
#Sta/Elev= 30
  4803.2  952.13  4817.7  951.20  4841.2  947.71  4864.8  941.28  4870.2  941.37
  4911.9  928.53  4917.3  926.64  4922.9  920.00  4933.8  917.64  4940.8  913.99
  4946.3  909.30  4966.6  895.88  4974.5  893.85  4975.0  893.35  4980.2  893.85
  4996.8  898.44  5022.5  901.31  5043.4  902.19  5092.7  898.76  5106.9  900.38
  5171.3  917.27  5220.7  928.83  5319.9  946.67  5347.8  953.39  5369.5  960.14
  5418.9  970.22  5496.7  995.38  5553.5 1009.52  5557.3 1011.57  5560.6 1011.57
#Mann=4,-1,0
  4803.2    0.05       0  4966.6    0.12       0  4974.5    0.07       0
  4980.2    0.12       0
Bank Sta=4974.5,4980.2
Exp/Cntr=0.3,0.1

Type RM Length L Ch R = 1,7625,125,125,125
BEGIN DESCRIPTION:
Mapping XS 8d651263
END DESCRIPTION:
XS GIS Cut Line= 3
      2920935.49     10164846.21      2921324.35     10164950.37
      2921871.87     10165061.26
#Sta/Elev= 30
  4432.7  972.65  4470.0  968.39  4505.4  964.10  4546.8  957.59  4554.0  955.21
  4670.0  940.36  4681.4  937.98  4702.1  936.97  4714.1  933.70  4754.1  927.90
  4858.3  915.79  4918.3  908.93  4924.0  906.96  4929.1  907.48  4971.5  893.80
  4974.7  892.18  5007.2  890.59  5007.7  890.09  5013.0  890.59  5050.9  893.03
  5091.7  892.70  5121.7  897.57  5126.8  895.49  5132.5  897.87  5171.2  901.57
  5177.5  900.35  5223.1  903.97  5285.6  914.88  5329.6  919.52  5393.9  931.57
#Mann=8,-1,0
  4432.7    0.05       0  4470.0    0.12       0  4670.0    0.05       0
  4858.3    0.12       0  4971.5    0.05       0  5007.2    0.05       0
  5013.0    0.05       0  5171.2    0.12       0
Bank Sta=5007.2,5013
Exp/Cntr=0.3,0.1

Type RM Length L Ch R = 1,7500,500,500,500
BEGIN DESCRIPTION:
HORSESHOE CREEK 15.0
END DESCRIPTION:
XS GIS Cut Line= 3
      2921013.32     10164967.66      2921410.79     10165072.66
      2921805.66     10165303.10
#Sta/Elev= 30
  4588.9  953.41  4633.9  945.05  4704.0  935.95  4709.2  932.62  4859.9  911.56
  4865.1  908.26  4900.2  901.31  4912.0  896.41  4945.6  887.16  4983.0  885.91
  4983.5  885.41  4988.8  885.91  5005.4  886.75  5032.6  892.25  5054.1  893.06
  5098.3  889.95  5107.1  887.24  5150.1  890.99  5160.1  893.54  5165.8  894.96
  5171.5  892.75  5174.6  893.39  5187.3  898.49  5230.3  901.73  5246.0  905.29
  5383.1  923.88  5384.9  924.14  5422.1  928.45  5427.9  927.09  5457.2  931.06
#Mann=7,-1,0
  4588.9    0.12       0  4983.0    0.07       0  4988.8    0.12       0
  5160.1    0.05       0  5174.6    0.12       0  5383.1    0.05       0
  5384.9    0.12       0
Bank Sta=4983,4988.8
Exp/Cntr=0.3,0.1

Type RM Length L Ch R = 1,7000,500,500,500
BEGIN DESCRIPTION:
HORSESHOE CREEK 14.0
END DESCRIPTION:
XS GIS Cut Line= 3
      2920805.71     10165203.14      2921025.34     10165385.86
      2921255.71     10165503.13
#Sta/Elev= 30
  4714.3  953.99  4717.5  953.99  4721.4  952.24  4742.2  948.41  4770.9  940.53
  4792.3  935.93  4799.5  935.83  4834.7  925.17  4856.8  917.42  4863.3  916.48
  4877.7  909.33  4898.5  904.19  4906.3  900.21  4927.1  892.44  4955.8  883.83
  4976.6  876.53  4990.9  872.20  5002.6  871.03  5003.1  870.53  5008.4  871.03
  5022.1  873.59  5034.1  877.08  5101.4  882.80  5111.1  884.94  5133.3  887.70
  5168.7  889.37  5200.1  892.72  5227.9  893.72  5236.0  895.35  5258.5  896.39
#Mann=3,-1,0
  4714.3    0.12       0  5002.6    0.07       0  5008.4    0.12       0
Bank Sta=5002.6,5008.4
Exp/Cntr=0.3,0.1