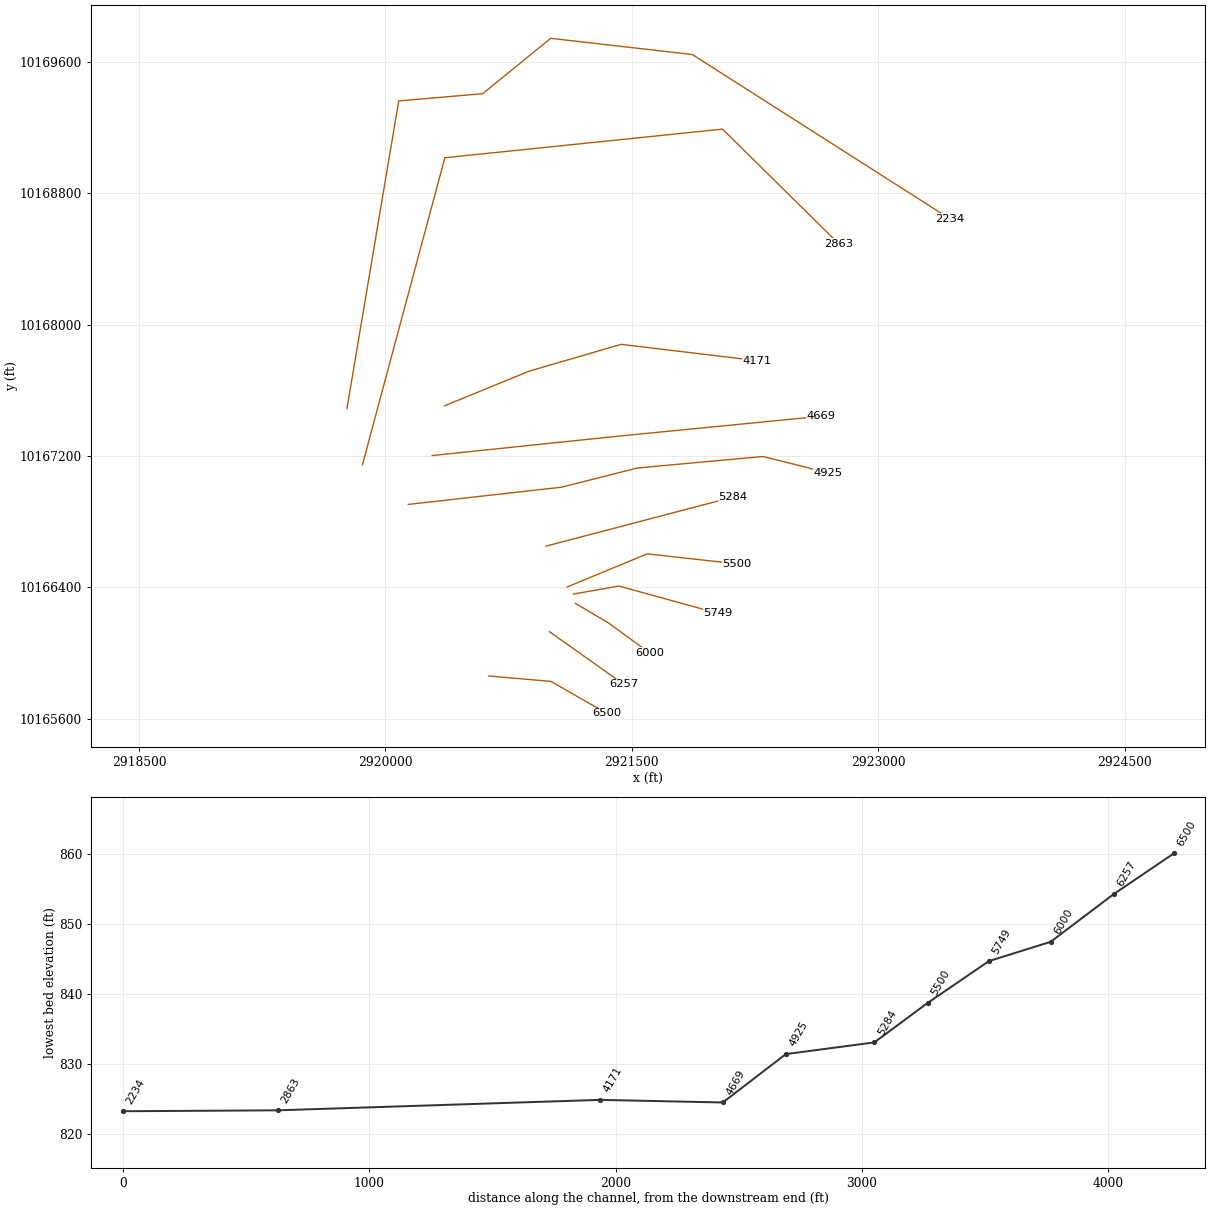
HEC-RAS study HORSESHOE CREEK.prj: HORSESHOE CREEK Base Level Engineering

--- HORSESHOE CREEK.g01 (geometry) --- (continued)

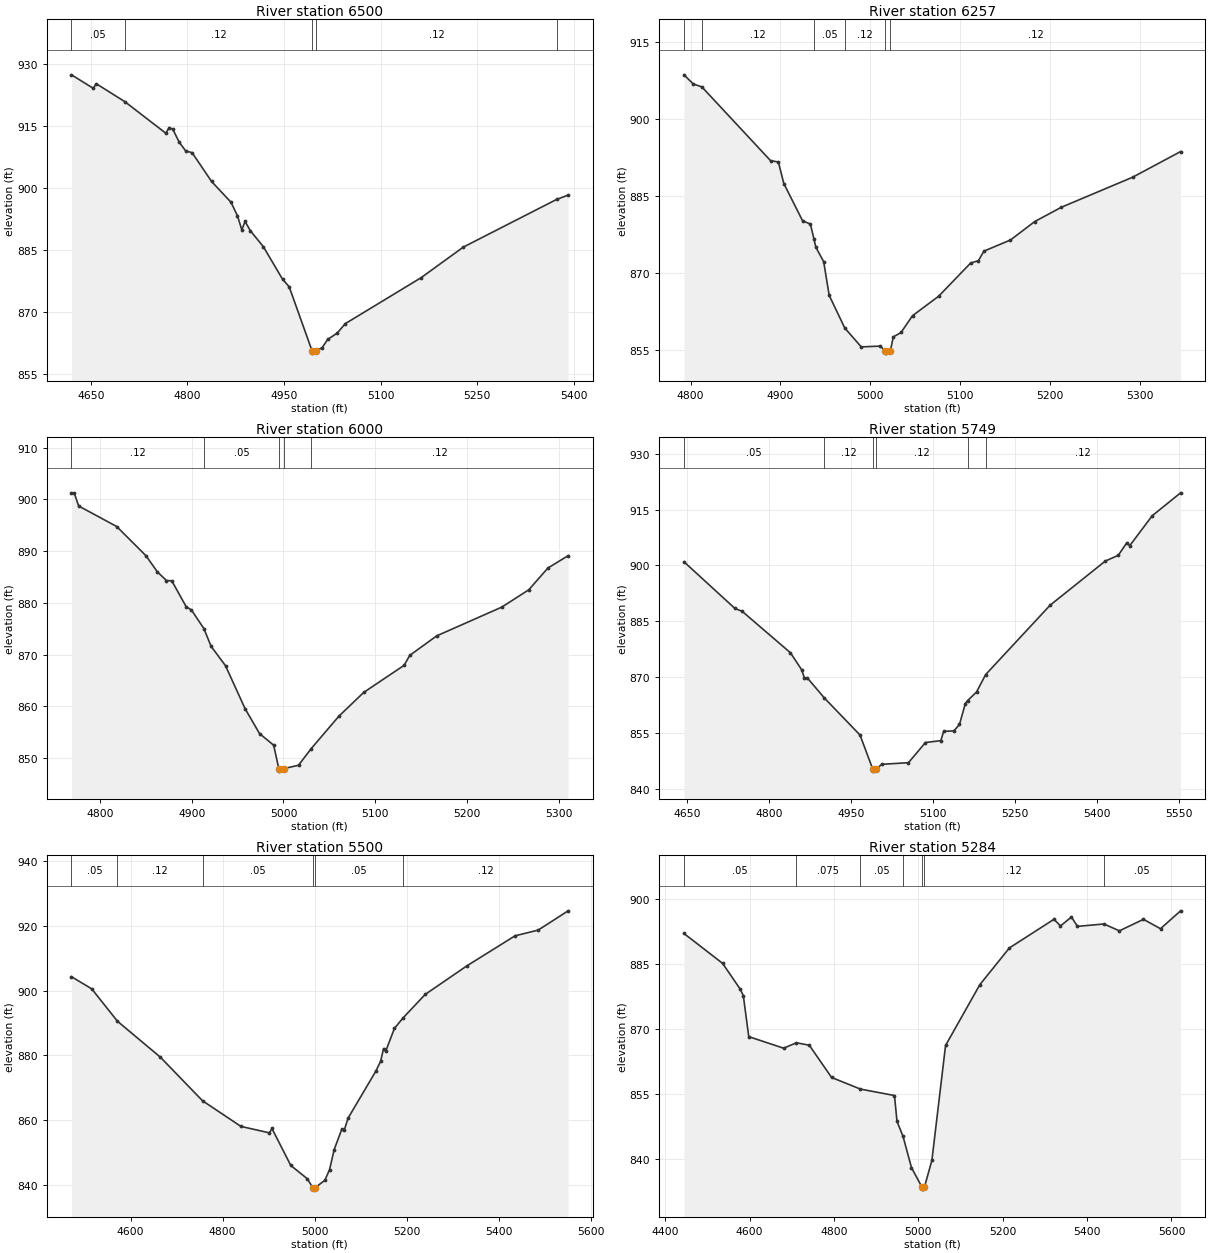
Type RM Length L Ch R = 1,6500,243,243,243
BEGIN DESCRIPTION:
HORSESHOE CREEK 13.0
END DESCRIPTION:
XS GIS Cut Line= 3
      2920629.06     10165861.19      2921007.63     10165828.25
      2921346.75     10165633.62
#Sta/Elev= 30
  4620.0  927.27  4653.6  924.03  4658.6  925.11  4703.0  920.77  4766.5  913.16
  4771.5  914.51  4777.2  914.15  4787.3  910.99  4797.3  908.89  4807.3  908.47
  4837.4  901.53  4867.6  896.51  4877.6  893.26  4884.4  889.84  4889.5  891.87
  4897.7  889.61  4917.7  885.81  4947.9  877.86  4957.9  876.11  4993.6  860.57
  4994.1  860.07  4999.5  860.57  5009.3  861.42  5017.7  863.38  5032.3  864.88
  5045.1  867.19  5163.0  878.31  5228.4  885.68  5373.5  897.21  5391.0  898.22
#Mann=5,-1,0
  4620.0    0.05       0  4703.0    0.12       0  4993.6    0.07       0
  4999.5    0.12       0  5373.5    0.05       0
Bank Sta=4993.6,4999.5
Exp/Cntr=0.3,0.1

Type RM Length L Ch R = 1,6257,257,257,257
BEGIN DESCRIPTION:
Mapping XS 44ff8da6
END DESCRIPTION:
XS GIS Cut Line= 2
      2920997.92     10166130.96      2921449.31     10165811.50
#Sta/Elev= 30
  4792.7  908.66  4803.0  906.89  4812.7  906.29  4889.1  891.90  4897.8  891.63
  4903.9  887.43  4924.8  880.14  4933.5  879.51  4937.4  876.61  4939.6  874.97
  4948.3  872.15  4954.4  865.59  4971.7  859.22  4990.1  855.52  5011.0  855.67
  5016.7  854.80  5017.2  854.30  5022.6  854.80  5025.8  857.47  5034.4  858.33
  5047.2  861.61  5076.2  865.40  5111.9  871.89  5120.6  872.36  5126.7  874.22
  5156.3  876.40  5183.3  880.00  5212.9  882.79  5292.2  888.65  5345.7  893.67
#Mann=6,-1,0
  4792.7    0.05       0  4812.7    0.12       0  4937.4    0.05       0
  4971.7    0.12       0  5016.7    0.07       0  5022.6    0.12       0
Bank Sta=5016.7,5022.6
Exp/Cntr=0.3,0.1

Type RM Length L Ch R = 1,6000,251,251,251
BEGIN DESCRIPTION:
HORSESHOE CREEK 12.0
END DESCRIPTION:
XS GIS Cut Line= 3
      2921155.72     10166303.09      2921354.90     10166185.89
      2921605.67     10166003.13
#Sta/Elev= 30
  4768.9  901.26  4771.8  901.26  4776.7  898.72  4818.2  894.75  4850.1  889.10
  4862.5  885.99  4872.4  884.31  4878.2  884.26  4893.9  879.26  4899.7  878.61
  4913.2  875.03  4921.1  871.59  4936.8  867.84  4958.2  859.52  4973.9  854.73
  4989.3  852.48  4994.9  847.97  4995.4  847.47  5000.8  847.97  5016.4  848.61
  5030.2  851.82  5060.4  858.09  5087.6  862.70  5131.5  867.92  5137.7  869.85
  5167.0  873.61  5238.1  879.18  5267.4  882.52  5288.3  886.73  5310.3  889.11
#Mann=5,-1,0
  4768.9    0.12       0  4913.2    0.05       0  4994.9    0.05       0
  5000.8    0.05       0  5030.2    0.12       0
Bank Sta=4994.9,5000.8
Exp/Cntr=0.3,0.1

Type RM Length L Ch R = 1,5749,249,249,249
BEGIN DESCRIPTION:
Mapping XS 822b1a08
END DESCRIPTION:
XS GIS Cut Line= 3
      2921143.77     10166360.09      2921421.57     10166408.70
      2922025.69     10166242.05
#Sta/Elev= 30
  4643.6  900.96  4736.9  888.42  4750.1  887.65  4838.4  876.52  4858.7  872.01
  4864.0  869.76  4869.1  869.80  4900.6  864.35  4965.8  854.40  4989.1  845.21
  4989.6  844.71  4995.1  845.21  5005.4  846.54  5054.4  846.98  5085.5  852.40
  5113.6  852.90  5118.8  855.40  5137.4  855.52  5147.7  857.24  5158.4  862.84
  5162.6  863.67  5178.9  865.96  5195.6  870.65  5313.7  889.31  5414.5  901.15
  5438.2  902.69  5454.0  906.08  5459.2  905.28  5500.4  913.33  5552.3  919.49
#Mann=6,-1,0
  4643.6    0.05       0  4900.6    0.12       0  4989.1    0.07       0
  4995.1    0.12       0  5162.6    0.05       0  5195.6    0.12       0
Bank Sta=4989.1,4995.1
Exp/Cntr=0.3,0.1

Type RM Length L Ch R = 1,5500,216,216,216
BEGIN DESCRIPTION:
HORSESHOE CREEK 11.0
END DESCRIPTION:
XS GIS Cut Line= 3
      2921105.73     10166403.13      2921593.80     10166604.81
      2922140.31     10166543.89
#Sta/Elev= 30
  4471.9  904.31  4515.8  900.57  4571.7  890.56  4664.7  879.49  4756.3  866.02
  4839.7  858.10  4901.6  856.11  4907.0  857.46  4947.9  846.05  4984.1  841.90
  4995.3  839.24  4995.8  838.74  5001.4  839.24  5022.0  841.49  5032.1  844.76
  5042.1  850.96  5058.9  857.33  5063.9  856.91  5072.3  860.67  5132.7  875.20
  5142.8  878.19  5149.3  882.13  5154.3  881.44  5172.9  888.36  5191.6  891.59
  5239.7  898.85  5330.1  907.66  5434.6  916.93  5484.9  918.70  5549.9  924.65
#Mann=6,-1,0
  4471.9    0.05       0  4571.7    0.12       0  4756.3    0.05       0
  4995.3    0.05       0  5001.4    0.05       0  5191.6    0.12       0
Bank Sta=4995.3,5001.4
Exp/Cntr=0.3,0.1

Type RM Length L Ch R = 1,5284,359,359,359
BEGIN DESCRIPTION:
Mapping XS 9a69905a
END DESCRIPTION:
XS GIS Cut Line= 2
      2920977.11     10166651.76      2922116.01     10166950.37
#Sta/Elev= 30
  4444.2  892.15  4535.8  885.25  4577.1  879.37  4584.9  877.81  4597.8  868.33
  4680.5  865.66  4710.7  866.91  4741.3  866.35  4794.2  858.90  4862.6  856.22
  4943.3  854.73  4949.3  848.75  4963.5  845.33  4983.6  838.08  5008.3  833.62
  5008.8  833.12  5014.4  833.62  5032.0  839.76  5064.4  866.29  5145.7  880.33
  5215.7  888.81  5321.5  895.43  5336.8  893.89  5362.8  895.95  5377.2  893.79
  5439.8  894.34  5476.5  892.76  5533.6  895.42  5574.0  893.25  5621.6  897.38
#Mann=7,-1,0
  4444.2    0.05       0  4710.7   0.075       0  4862.6    0.05       0
  4963.5    0.12       0  5008.3    0.07       0  5014.4    0.12       0
  5439.8    0.05       0
Bank Sta=5008.3,5014.4
Exp/Cntr=0.3,0.1

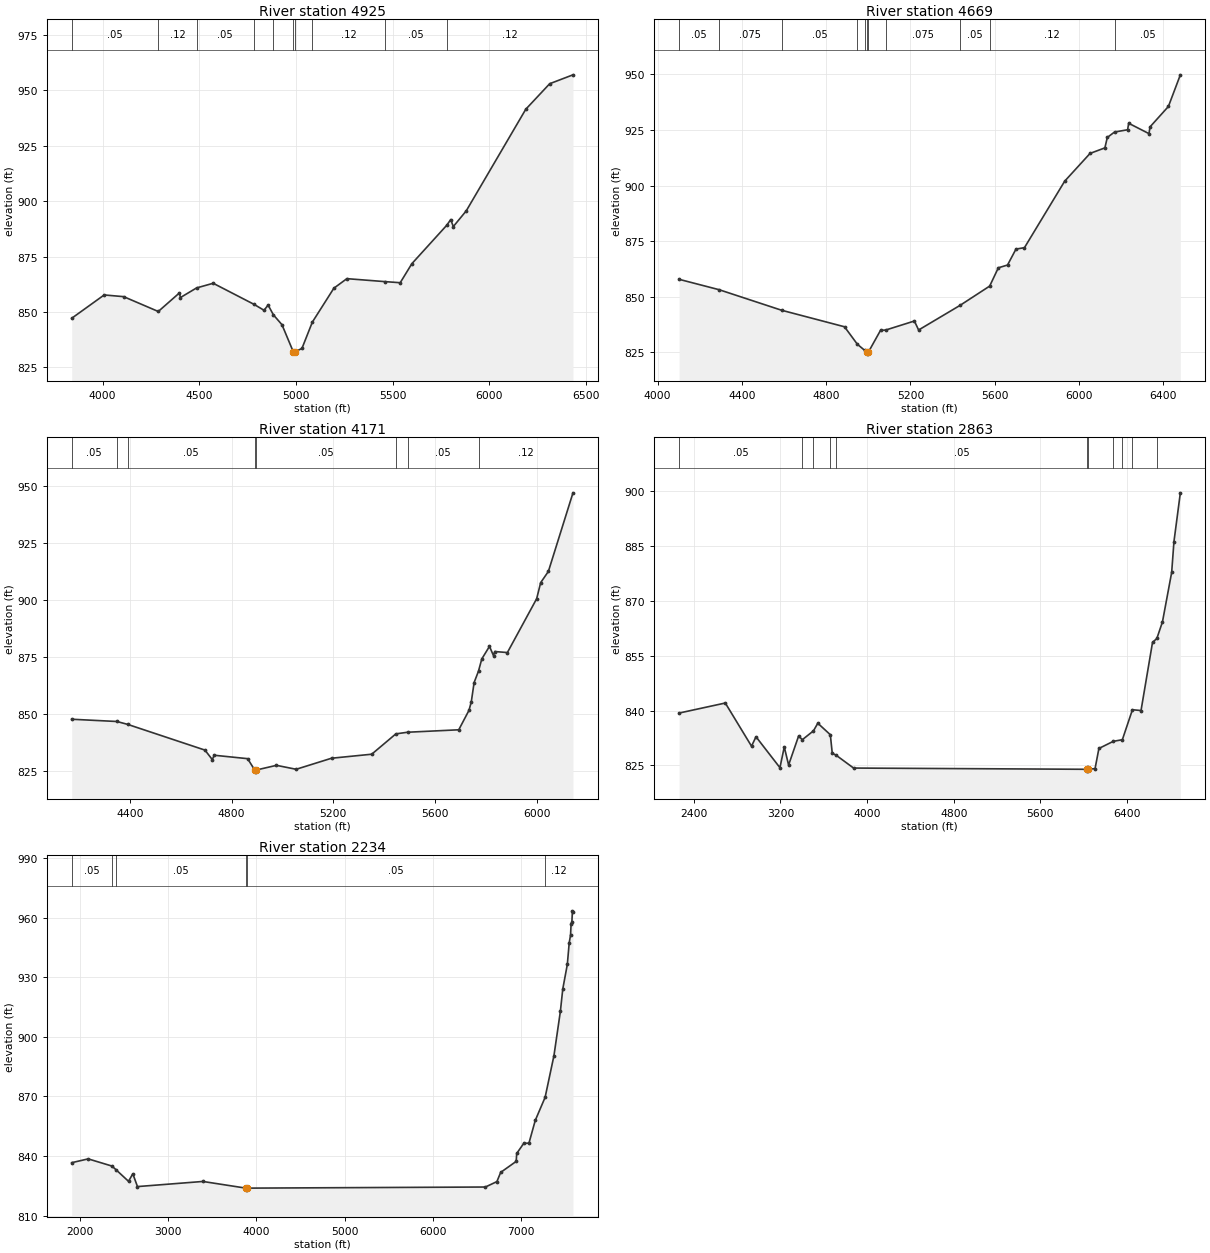
Type RM Length L Ch R = 1,4925,256,256,256
BEGIN DESCRIPTION:
Mapping XS 68086783
END DESCRIPTION:
XS GIS Cut Line= 5
      2920138.91     10166905.66      2921072.50     10167010.69
      2921533.47     10167127.39      2922297.86     10167197.41
      2922694.66     10167098.21
#Sta/Elev= 30
  3840.7  847.19  4008.5  857.71  4109.2  856.94  4288.2  850.25  4397.6  858.63
  4402.7  856.54  4486.0  860.87  4572.1  862.98  4782.6  853.50  4835.0  850.79
  4856.0  853.16  4883.4  848.73  4927.7  844.28  4986.7  831.96  4987.2  831.46
  4992.8  831.96  5031.0  833.58  5084.9  845.48  5196.1  860.76  5263.3  865.06
  5459.1  863.73  5539.1  863.23  5599.3  871.82  5779.5  889.14  5800.2  891.72
  5813.5  888.56  5880.5  895.66  6188.2  941.49  6311.9  953.02  6432.3  957.03
#Mann=10,-1,0
  3840.7    0.05       0  4288.2    0.12       0  4486.0    0.05       0
  4782.6   0.075       0  4883.4    0.05       0  4986.7    0.03       0
  4992.8    0.05       0  5084.9    0.12       0  5459.1    0.05       0
  5779.5    0.12       0
Bank Sta=4986.7,4992.8
Exp/Cntr=0.3,0.1

Type RM Length L Ch R = 1,4669,498,498,498
BEGIN DESCRIPTION:
Mapping XS 78703e7d
END DESCRIPTION:
XS GIS Cut Line= 3
      2920284.76     10167203.25      2921405.10     10167319.95
      2922652.21     10167442.33
#Sta/Elev= 30
  4102.1  857.78  4291.9  853.11  4588.3  843.87  4887.3  836.42  4948.4  828.55
  4983.6  825.77  4994.8  825.06  4995.3  824.56  5000.9  825.06  5058.2  834.80
  5082.4  834.94  5219.0  839.01  5239.1  834.97  5435.4  846.03  5576.4  854.73
  5617.6  862.97  5661.2  864.21  5701.3  871.39  5741.5  872.02  5932.5  901.95
  6053.0  914.45  6123.4  916.94  6134.8  921.63  6169.0  924.06  6231.2  925.10
  6236.3  928.02  6332.7  923.35  6337.7  926.40  6424.8  935.57  6481.6  949.82
#Mann=11,-1,0
  4102.1    0.05       0  4291.9   0.075       0  4588.3    0.05       0
  4948.4   0.075       0  4983.6    0.05       0  4994.8    0.03       0
  5000.9    0.05       0  5082.4   0.075       0  5435.4    0.05       0
  5576.4    0.12       0  6169.0    0.05       0
Bank Sta=4994.8,5000.9
Exp/Cntr=0.3,0.1

Type RM Length L Ch R = 1,4171,1308,1308,1308
BEGIN DESCRIPTION:
Mapping XS a9256bd6
END DESCRIPTION:
XS GIS Cut Line= 4
      2920360.67     10167506.69      2920874.11     10167716.73
      2921434.27     10167880.11      2922261.81     10167781.04
#Sta/Elev= 30
  4171.0  847.70  4348.6  846.71  4390.5  845.46  4695.0  834.16  4723.9  830.00
  4731.6  831.90  4862.8  830.40  4890.8  825.43  4891.3  824.93  4897.3  825.43
  4976.4  827.47  5053.8  825.74  5192.9  830.59  5351.0  832.35  5446.0  841.28
  5492.3  842.00  5693.4  843.07  5733.7  851.63  5742.7  855.34  5753.8  863.80
  5771.1  868.84  5784.0  874.16  5814.2  879.68  5830.1  875.60  5835.1  877.41
  5884.7  876.97  5999.8  900.58  6015.7  907.66  6045.9  912.56  6142.7  947.06
#Mann=8,-1,0
  4171.0    0.05       0  4348.6   0.075       0  4390.5    0.05       0
  4890.8    0.03       0  4897.3    0.05       0  5446.0     0.1       0
  5492.3    0.05       0  5771.1    0.12       0
Bank Sta=4890.8,4897.3
Exp/Cntr=0.3,0.1

Type RM Length L Ch R = 1,2863,629,629,629
BEGIN DESCRIPTION:
Mapping XS 7006f8e7
END DESCRIPTION:
XS GIS Cut Line= 4
      2919859.81     10167147.43      2920361.41     10169016.15
      2922051.86     10169190.32      2922758.81     10168492.81
#Sta/Elev= 30
  2264.6  839.33  2691.1  842.08  2933.1  830.27  2974.6  832.84  3195.5  824.38
  3235.5  830.07  3275.4  825.11  3368.0  833.06  3402.3  832.04  3505.2  834.47
  3545.1  836.55  3660.7  833.40  3678.6  828.30  3711.1  827.86  3875.3  824.28
  6030.6  823.94  6031.1  823.44  6037.3  823.94  6104.6  824.13  6140.1  829.64
  6272.6  831.59  6356.6  832.04  6449.6  840.24  6528.9  840.02  6635.0  858.66
  6675.1  859.74  6726.9  864.30  6811.8  877.81  6833.0  886.27  6892.0  899.60
#Mann=11,-1,0
  2264.6    0.05       0  3402.3   0.075       0  3505.2    0.05       0
  3660.7   0.075       0  3711.1    0.05       0  6030.6    0.03       0
  6037.3    0.05       0  6272.6   0.075       0  6356.6    0.05       0
  6449.6   0.075       0  6675.1    0.12       0
Bank Sta=6030.6,6037.3
Exp/Cntr=0.3,0.1

Type RM Length L Ch R = 1,2234,0,0,0
BEGIN DESCRIPTION:
HORSESHOE CREEK 8.0
END DESCRIPTION:
XS GIS Cut Line= 6
      2919765.46     10167489.21      2920080.54     10169362.21
      2920591.68     10169405.94      2921005.64     10169743.01
      2921867.65     10169644.52      2923435.73     10168644.48
#Sta/Elev= 30
  1911.7  836.62  2098.2  838.53  2366.8  834.92  2413.5  833.05  2554.5  827.24
  2603.2  831.03  2655.9  824.59  3396.2  827.17  3883.0  823.81  3883.5  823.31
  3889.9  823.81  6593.9  824.37  6724.2  827.10  6766.9  831.73  6942.5  837.27
  6948.5  841.27  7027.8  846.32  7087.1  846.48  7158.3  857.88  7269.9  869.51
  7369.9  890.48  7442.7  912.80  7469.8  924.03  7521.4  936.41  7542.5  947.24
  7557.8  951.19  7563.7  956.50  7573.0  957.89  7578.9  963.36  7585.3  962.89
#Mann=6,-1,0
  1911.7    0.05       0  2366.8    0.12       0  2413.5    0.05       0
  3883.0    0.03       0  3889.9    0.05       0  7269.9    0.12       0
Bank Sta=3883,3889.9
Exp/Cntr=0.3,0.1

Chan Stop Cuts=-1