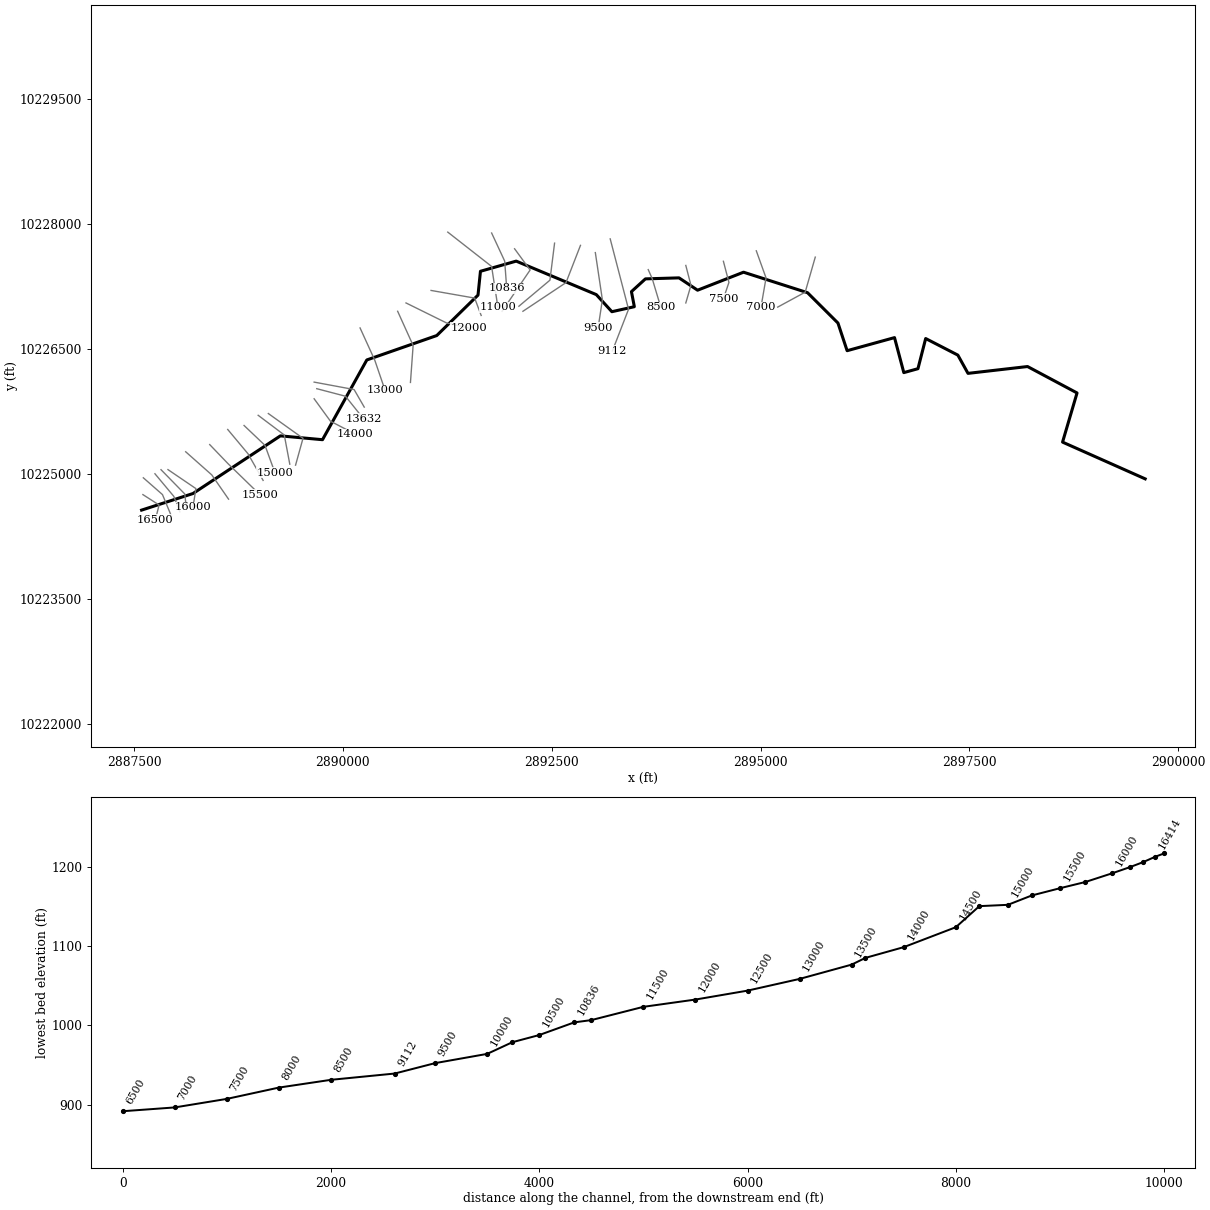
--- INKS 02.prj (project) ---

Proj Title=INKS 02 Base Level Engineering
Current Plan=p01
Default Exp/Contr=0.3,0.1
English Units
Geom File=g01
Flow File=f01
Plan File=p01
BEGIN DESCRIPTION:
INKS 02
END DESCRIPTION:

--- INKS 02.p01 (plan) ---

Plan Title=Multiple Run
Short Identifier=Multiple
Geom File=g01
Flow File=f01
Subcritical Flow
K Sum by GR= 0
Std Step Tol= 0.01
Critical Tol= 0.01
Num of Std Step Trials= 20
Max Error Tol= 0.3
Flow Tol Ratio= 0.001
Split Flow NTrial= 30
Split Flow Tol= 0.02
Split Flow Ratio= 0.02
Log Output Level= 0
Friction Slope Method= 1
Unsteady Friction Slope Method= 2
Unsteady Bridges Friction Slope Method= 1
Parabolic Critical Depth
Global Vel Dist=  1 , 1 , 1
Global Log Level= 0
CheckData=True
Encroach Param= -1, 0, 0, 0
BEGIN DESCRIPTION:
Multiple Run
END DESCRIPTION:

--- INKS 02.f01 (steady flow) ---

Flow Title=Multiple
Number of Profiles=7
Profile Names=10-year,25-year,50-year,1pct_min,100-year,1pct_plu,500-year
River Rch & RM= INKS 02,Reach-1,16500
     401     639    1552    1379    2204    3522    3229
River Rch & RM= INKS 02,Reach-1,9500
     757    1275    2692    2024    3866    7382    5631
Boundary for River Rch & Prof#=INKS 02,Reach-1,1
Up Type=0
Dn Type=3
Dn Slope=0.005
Boundary for River Rch & Prof#=INKS 02,Reach-1,2
Up Type=0
Dn Type=3
Dn Slope=0.005
Boundary for River Rch & Prof#=INKS 02,Reach-1,3
Up Type=0
Dn Type=3
Dn Slope=0.005
Boundary for River Rch & Prof#=INKS 02,Reach-1,4
Up Type=0
Dn Type=3
Dn Slope=0.005
Boundary for River Rch & Prof#=INKS 02,Reach-1,5
Up Type=0
Dn Type=3
Dn Slope=0.005
Boundary for River Rch & Prof#=INKS 02,Reach-1,6
Up Type=0
Dn Type=3
Dn Slope=0.005
Boundary for River Rch & Prof#=INKS 02,Reach-1,7
Up Type=0
Dn Type=3
Dn Slope=0.005

--- INKS 02.g01 (geometry) ---

Geom Title=Existing Conditions

River Reach=INKS 02,Reach-1
Reach XY= 30
      2887590.00     10224567.00      2888205.00     10224766.00
      2889251.50     10225458.00      2889756.00     10225412.00
      2890286.50     10226369.00      2891124.00     10226662.00
      2891617.75     10227147.00      2891647.00     10227433.00
      2892075.00     10227555.00      2893034.25     10227153.00
      2893220.50     10226948.00      2893489.50     10227008.00
      2893454.75     10227189.00      2893622.25     10227342.00
      2894024.25     10227354.00      2894246.50     10227206.00
      2894796.75     10227422.00      2895563.00     10227176.00
      2895927.25     10226812.00      2896037.00     10226480.00
      2896604.50     10226637.00      2896715.75     10226217.00
      2896885.00     10226264.00      2896977.50     10226626.00
      2897362.75     10226427.00      2897484.25     10226208.00
      2898197.00     10226290.00      2898789.75     10225973.00
      2898616.25     10225383.00      2899605.50     10224942.00

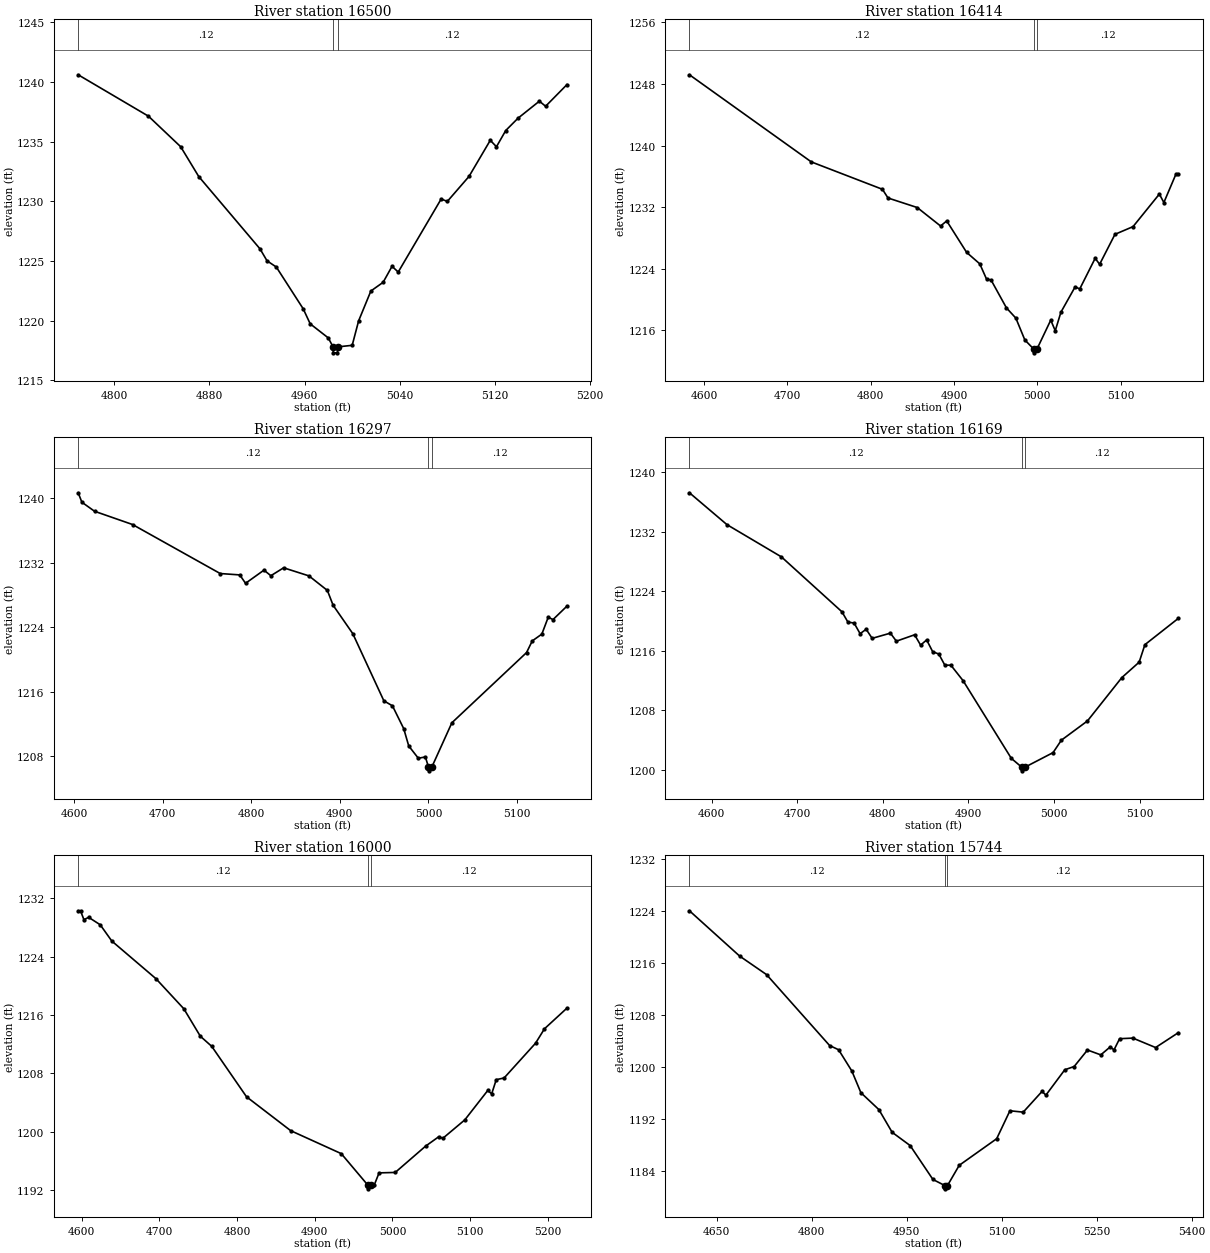
Type RM Length L Ch R = 1,16500,86,86,86
BEGIN DESCRIPTION:
INKS 02 33.0
END DESCRIPTION:
XS GIS Cut Line= 3
      2887605.65     10224753.13      2887799.35     10224628.38
      2887755.69     10224453.14
#Sta/Elev= 30
  4769.6 1240.61  4828.7 1237.14  4855.8 1234.58  4871.0 1232.08  4922.5 1226.02
  4928.4 1225.02  4936.2 1224.50  4958.8 1221.00  4964.7 1219.74  4979.9 1218.56
  4983.9 1217.81  4984.1 1217.31  4987.6 1217.31  4987.9 1217.81  5000.0 1217.94
  5005.4 1219.99  5015.7 1222.49  5026.0 1223.22  5033.5 1224.56  5038.7 1224.08
  5074.8 1230.20  5080.0 1230.00  5098.2 1232.09  5116.1 1235.12  5121.3 1234.58
  5129.1 1235.94  5139.4 1236.97  5157.4 1238.40  5162.6 1237.97  5180.6 1239.79
#Mann=3,-1,0
  4769.6    0.12       0  4983.9    0.07       0  4987.9    0.12       0
Bank Sta=4983.9,4987.9
Exp/Cntr=0.3,0.1

Type RM Length L Ch R = 1,16414,117,117,117
BEGIN DESCRIPTION:
Mapping XS 6442a5c1
END DESCRIPTION:
XS GIS Cut Line= 3
      2887610.78     10224954.74      2887839.97     10224753.33
      2887947.61     10224492.91
#Sta/Elev= 30
  4582.4 1249.19  4728.7 1237.87  4814.1 1234.31  4820.8 1233.18  4855.9 1231.94
  4883.9 1229.54  4891.3 1230.20  4915.2 1226.11  4931.0 1224.62  4939.1 1222.64
  4944.5 1222.53  4963.0 1218.90  4974.3 1217.57  4985.1 1214.73  4995.7 1213.56
  4996.0 1213.06  4999.7 1213.56  5016.2 1217.31  5021.6 1215.93  5028.4 1218.34
  5045.5 1221.64  5051.0 1221.36  5069.5 1225.34  5074.9 1224.57  5093.3 1228.46
  5115.0 1229.46  5146.6 1233.69  5152.0 1232.59  5166.5 1236.28  5169.3 1236.28
#Mann=3,-1,0
  4582.4    0.12       0  4995.7    0.07       0  4999.7    0.12       0
Bank Sta=4995.7,4999.7
Exp/Cntr=0.3,0.1

Type RM Length L Ch R = 1,16297,128,128,128
BEGIN DESCRIPTION:
Mapping XS ad3a7074
END DESCRIPTION:
XS GIS Cut Line= 3
      2887749.70     10225003.33      2887975.39     10224732.50
      2888047.68     10224546.60
#Sta/Elev= 30
  4604.5 1240.64  4608.7 1239.47  4623.0 1238.35  4665.9 1236.71  4764.9 1230.64
  4787.0 1230.47  4793.5 1229.43  4814.3 1231.06  4822.1 1230.37  4836.5 1231.35
  4865.1 1230.35  4885.9 1228.55  4892.4 1226.71  4914.6 1223.20  4949.7 1214.88
  4959.4 1214.26  4972.1 1211.44  4977.8 1209.29  4988.6 1207.77  4996.6 1207.93
  5000.0 1206.71  5000.2 1206.21  5004.0 1206.71  5026.5 1212.16  5110.8 1220.85
  5117.3 1222.30  5128.1 1223.14  5135.3 1225.23  5140.7 1224.94  5156.5 1226.61
#Mann=3,-1,0
  4604.5    0.12       0  5000.0    0.07       0  5004.0    0.12       0
Bank Sta=5000,5004
Exp/Cntr=0.3,0.1

Type RM Length L Ch R = 1,16169,169,169,169
BEGIN DESCRIPTION:
Mapping XS abf3e0b3
END DESCRIPTION:
XS GIS Cut Line= 3
      2887822.59     10225051.96      2888107.33     10224760.28
      2888124.64     10224597.62
#Sta/Elev= 30
  4574.0 1237.22  4617.8 1232.94  4681.5 1228.60  4752.2 1221.22  4759.2 1219.83
  4766.4 1219.71  4773.4 1218.28  4780.5 1218.87  4787.5 1217.65  4808.8 1218.35
  4815.8 1217.27  4837.1 1218.13  4844.1 1216.74  4851.2 1217.44  4858.2 1215.86
  4865.4 1215.54  4872.4 1214.05  4879.5 1214.04  4893.7 1211.97  4950.1 1201.52
  4962.2 1200.34  4962.5 1199.84  4966.2 1200.34  4998.9 1202.29  5008.6 1203.96
  5039.1 1206.55  5079.3 1212.38  5099.5 1214.45  5106.2 1216.80  5145.2 1220.33
#Mann=3,-1,0
  4574.0    0.12       0  4962.2    0.07       0  4966.2    0.12       0
Bank Sta=4962.2,4966.2
Exp/Cntr=0.3,0.1

Type RM Length L Ch R = 1,16000,256,256,256
BEGIN DESCRIPTION:
INKS 02 32.0
END DESCRIPTION:
XS GIS Cut Line= 3
      2887905.72     10225053.09      2888240.17     10224825.23
      2888205.68     10224603.09
#Sta/Elev= 30
  4595.3 1230.30  4598.3 1230.30  4602.7 1229.08  4608.8 1229.40  4623.7 1228.38
  4638.6 1226.15  4695.5 1220.98  4731.4 1216.85  4752.6 1213.09  4767.3 1211.70
  4812.1 1204.78  4869.0 1200.13  4934.1 1196.98  4968.4 1192.65  4968.6 1192.15
  4972.4 1192.65  4976.8 1192.73  4982.8 1194.34  5003.6 1194.40  5042.6 1198.00
  5059.8 1199.31  5064.9 1199.08  5093.2 1201.61  5122.8 1205.65  5127.8 1205.18
  5133.7 1207.13  5143.8 1207.36  5184.3 1212.13  5195.8 1214.11  5224.8 1216.95
#Mann=3,-1,0
  4595.3    0.12       0  4968.4    0.07       0  4972.4    0.12       0
Bank Sta=4968.4,4972.4
Exp/Cntr=0.3,0.1

Type RM Length L Ch R = 1,15744,244,244,244
BEGIN DESCRIPTION:
Mapping XS cacdd00a
END DESCRIPTION:
XS GIS Cut Line= 3
      2888117.75     10225267.22      2888430.25     10224989.45
      2888631.04     10224698.64
#Sta/Elev= 30
  4607.3 1223.98  4686.4 1217.02  4729.0 1214.16  4828.5 1203.25  4842.7 1202.60
  4863.6 1199.33  4877.9 1195.99  4906.3 1193.39  4927.2 1189.90  4955.6 1187.86
  4991.6 1182.64  5010.5 1181.70  5010.7 1181.20  5014.5 1181.70  5033.1 1184.82
  5092.2 1188.91  5113.1 1193.21  5134.1 1193.00  5163.8 1196.19  5169.9 1195.62
  5199.7 1199.52  5214.5 1200.02  5235.5 1202.56  5256.5 1201.81  5271.3 1203.03
  5277.4 1202.58  5286.2 1204.30  5307.2 1204.39  5343.0 1202.94  5378.8 1205.22
#Mann=3,-1,0
  4607.3    0.12       0  5010.5    0.07       0  5014.5    0.12       0
Bank Sta=5010.5,5014.5
Exp/Cntr=0.3,0.1

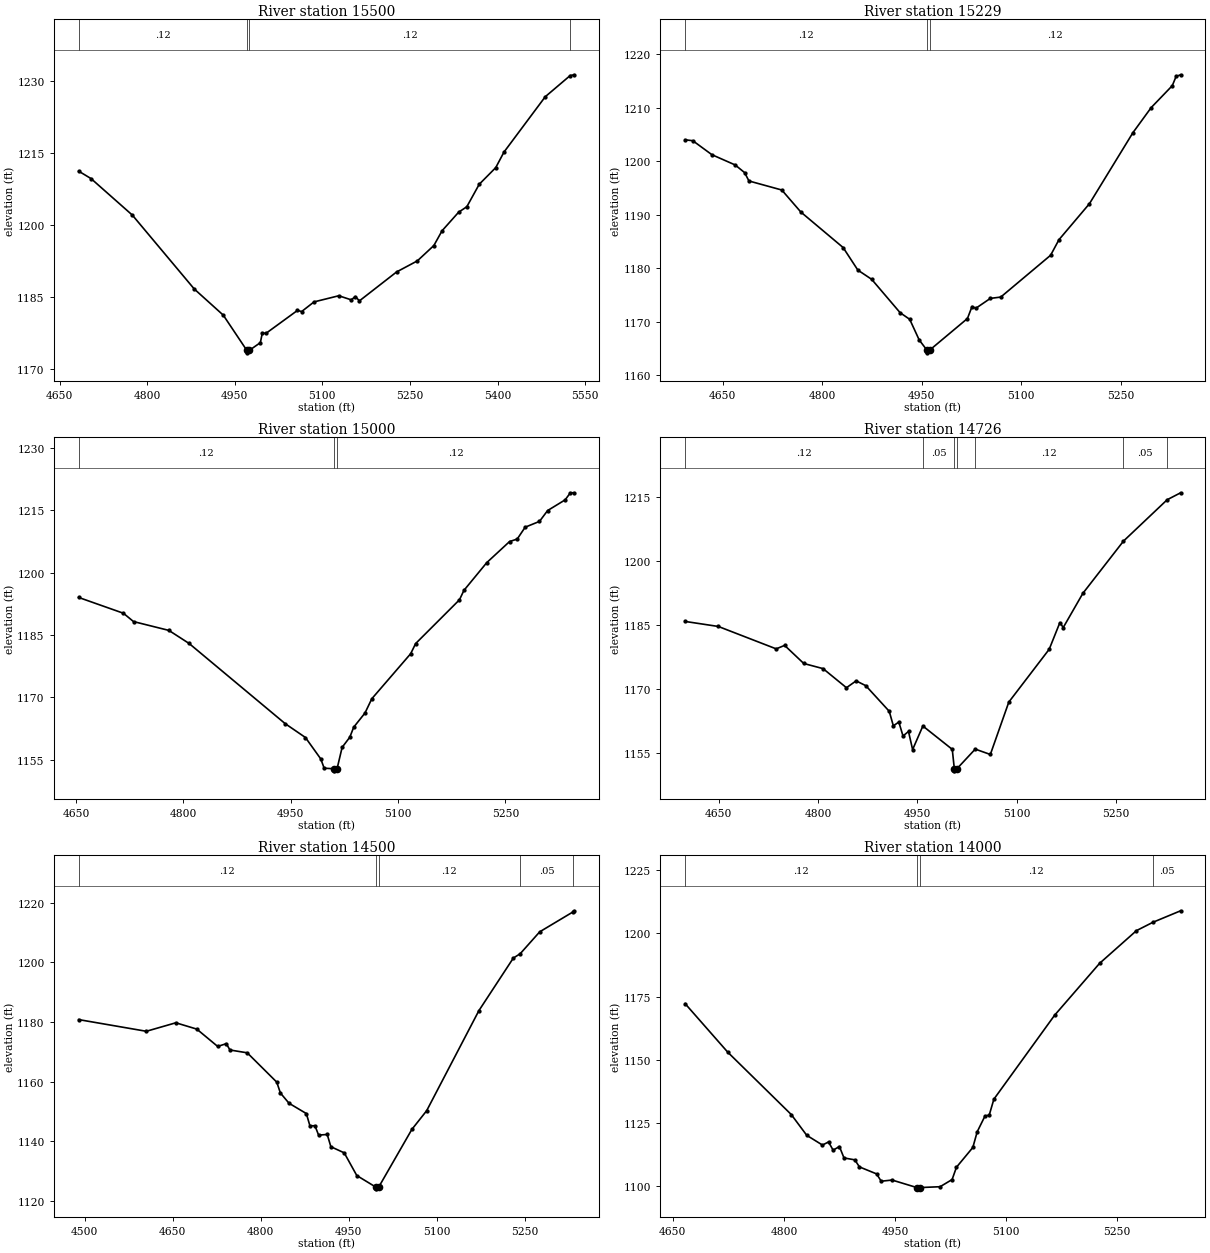
Type RM Length L Ch R = 1,15500,271,271,271
BEGIN DESCRIPTION:
INKS 02 31.0
END DESCRIPTION:
XS GIS Cut Line= 3
      2888405.69     10225353.11      2888625.22     10225123.88
      2889005.65     10224753.14
#Sta/Elev= 30
  4682.6 1211.19  4703.8 1209.64  4774.6 1202.03  4880.6 1186.64  4930.3 1181.19
  4970.7 1173.84  4971.0 1173.34  4974.7 1173.84  4993.8 1175.46  4997.1 1177.43
  5003.8 1177.43  5057.4 1182.18  5064.5 1181.94  5085.7 1183.95  5128.1 1185.23
  5149.4 1184.38  5156.4 1185.06  5163.5 1184.17  5227.1 1190.19  5262.6 1192.49
  5290.9 1195.69  5305.0 1198.77  5333.3 1202.63  5347.4 1203.78  5368.6 1208.45
  5396.9 1211.92  5411.0 1215.16  5481.7 1226.69  5524.3 1231.09  5531.2 1231.26
#Mann=4,-1,0
  4682.6    0.12       0  4970.7    0.07       0  4974.7    0.12       0
  5524.3    0.05       0
Bank Sta=4970.7,4974.7
Exp/Cntr=0.3,0.1

Type RM Length L Ch R = 1,15229,229,229,229
BEGIN DESCRIPTION:
Mapping XS bfa06938
END DESCRIPTION:
XS GIS Cut Line= 3
      2888621.20     10225534.61      2888864.28     10225242.92
      2889044.81     10224923.51
#Sta/Elev= 30
  4593.6 1204.02  4605.2 1203.85  4633.9 1201.24  4669.0 1199.32  4683.3 1197.88
  4689.8 1196.32  4739.3 1194.63  4768.0 1190.51  4831.7 1183.87  4853.9 1179.65
  4874.7 1177.93  4917.6 1171.68  4932.0 1170.45  4946.3 1166.59  4958.0 1164.68
  4958.3 1164.18  4962.0 1164.68  5019.0 1170.60  5025.9 1172.84  5031.6 1172.51
  5053.5 1174.36  5069.2 1174.61  5144.3 1182.43  5156.9 1185.34  5202.8 1192.07
  5268.4 1205.37  5295.8 1210.04  5327.6 1214.14  5333.4 1215.88  5340.2 1216.18
#Mann=3,-1,0
  4593.6    0.12       0  4958.0    0.07       0  4962.0    0.12       0
Bank Sta=4958,4962
Exp/Cntr=0.3,0.1

Type RM Length L Ch R = 1,15000,274,274,274
BEGIN DESCRIPTION:
INKS 02 30.0
END DESCRIPTION:
XS GIS Cut Line= 3
      2888816.72     10225582.54      2889067.67     10225343.62
      2889185.67     10225018.26
#Sta/Elev= 30
  4653.5 1194.03  4716.1 1190.23  4730.2 1188.23  4779.6 1186.11  4807.9 1182.97
  4942.2 1163.70  4970.5 1160.37  4991.9 1155.23  4996.7 1152.99  5010.7 1152.86
  5010.9 1152.36  5014.7 1152.86  5021.8 1158.01  5032.5 1160.44  5038.0 1162.86
  5053.7 1166.25  5063.3 1169.69  5117.6 1180.51  5124.5 1182.94  5185.8 1193.47
  5192.0 1195.72  5223.9 1202.39  5255.8 1207.46  5266.5 1208.06  5277.6 1210.91
  5297.6 1212.30  5309.0 1214.91  5333.5 1217.48  5340.8 1219.18  5346.1 1219.18
#Mann=3,-1,0
  4653.5    0.12       0  5010.7    0.07       0  5014.7    0.12       0
Bank Sta=5010.7,5014.7
Exp/Cntr=0.3,0.1

Type RM Length L Ch R = 1,14726,226,226,226
BEGIN DESCRIPTION:
Mapping XS 0737b92c
END DESCRIPTION:
XS GIS Cut Line= 3
      2888985.79     10225704.73      2889298.30     10225468.61
      2889364.25     10225118.05
#Sta/Elev= 30
  4599.2 1185.78  4649.4 1184.60  4736.8 1179.34  4749.5 1180.16  4778.4 1175.91
  4807.6 1174.70  4842.9 1170.22  4857.5 1171.83  4872.1 1170.70  4907.5 1164.69
  4913.7 1161.28  4922.0 1162.16  4928.3 1158.89  4936.6 1159.95  4942.8 1155.70
  4958.3 1161.23  5002.7 1155.75  5005.8 1151.21  5006.0 1150.71  5009.8 1151.21
  5037.4 1155.81  5060.2 1154.55  5088.1 1166.85  5149.1 1179.25  5165.2 1185.50
  5170.3 1184.35  5200.0 1192.39  5261.3 1204.64  5327.3 1214.35  5347.6 1215.98
#Mann=7,-1,0
  4599.2    0.12       0  4958.3    0.05       0  5005.8    0.03       0
  5009.8    0.05       0  5037.4    0.12       0  5261.3    0.05       0
  5327.3    0.12       0
Bank Sta=5005.8,5009.8
Exp/Cntr=0.3,0.1

Type RM Length L Ch R = 1,14500,500,500,500
BEGIN DESCRIPTION:
INKS 02 29.0
END DESCRIPTION:
XS GIS Cut Line= 3
      2889107.55     10225725.75      2889522.58     10225428.67
      2889433.46     10225106.57
#Sta/Elev= 30
  4489.6 1180.83  4605.0 1176.91  4655.3 1179.76  4691.0 1177.64  4726.6 1171.83
  4741.3 1172.76  4747.5 1170.64  4777.0 1169.69  4827.3 1159.86  4833.5 1156.22
  4848.2 1152.78  4877.7 1149.33  4883.8 1145.23  4892.4 1145.24  4898.6 1142.10
  4913.3 1142.32  4919.5 1138.22  4942.3 1136.15  4963.7 1128.55  4996.8 1124.59
  4997.1 1124.09  5000.8 1124.59  5057.6 1144.03  5082.8 1150.29  5171.8 1183.83
  5230.5 1201.46  5242.2 1202.91  5275.5 1210.26  5331.7 1216.87  5334.2 1217.31
#Mann=5,-1,0
  4489.6    0.12       0  4996.8    0.07       0  5000.8    0.12       0
  5242.2    0.05       0  5331.7    0.12       0
Bank Sta=4996.8,5000.8
Exp/Cntr=0.3,0.1

Type RM Length L Ch R = 1,14000,368,368,368
BEGIN DESCRIPTION:
INKS 02 28.0
END DESCRIPTION:
XS GIS Cut Line= 3
      2889655.70     10225903.09      2889851.72     10225633.41
      2890149.23     10225478.34
#Sta/Elev= 30
  4666.6 1172.19  4724.2 1152.97  4809.9 1128.31  4830.8 1120.09  4852.0 1116.23
  4860.2 1117.46  4866.4 1114.22  4874.9 1115.64  4881.1 1111.13  4895.7 1110.38
  4901.9 1107.59  4925.1 1104.82  4931.3 1101.92  4946.0 1102.39  4979.5 1099.41
  4979.8 1098.91  4983.5 1099.41  5010.8 1099.75  5027.0 1102.58  5032.9 1107.46
  5055.0 1115.27  5060.9 1121.49  5071.4 1127.72  5077.1 1128.06  5083.4 1134.38
  5165.4 1167.60  5226.1 1188.12  5275.9 1201.07  5298.1 1204.37  5335.5 1208.92
#Mann=4,-1,0
  4666.6    0.12       0  4979.5    0.07       0  4983.5    0.12       0
  5298.1    0.05       0
Bank Sta=4979.5,4983.5
Exp/Cntr=0.3,0.1

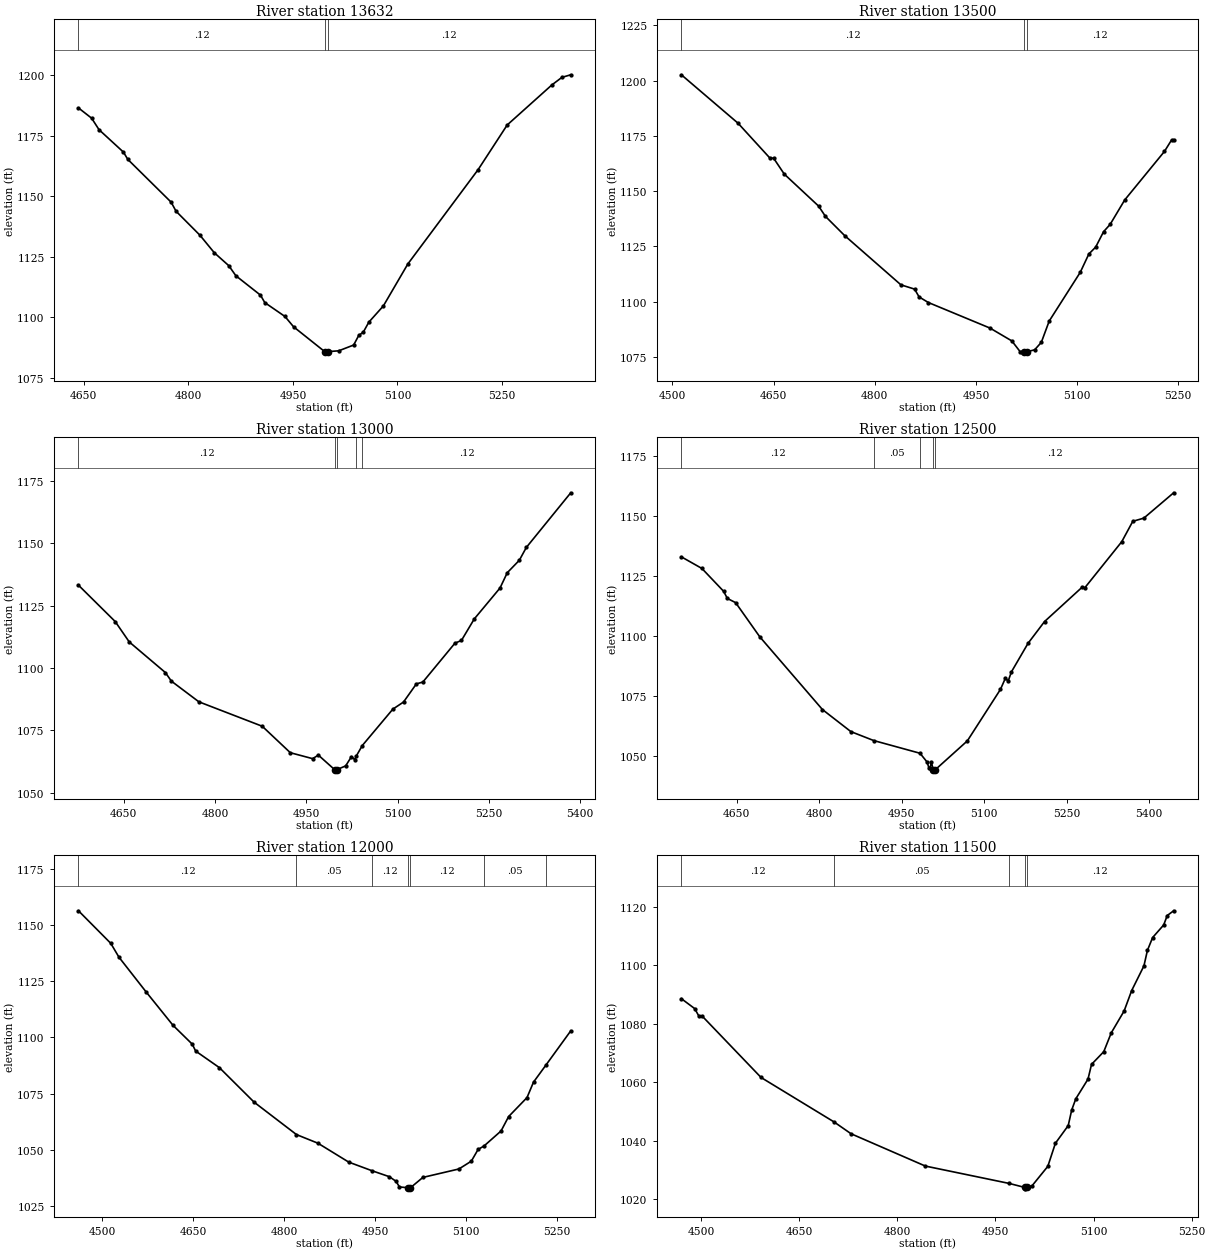
Type RM Length L Ch R = 1,13632,132,132,132
BEGIN DESCRIPTION:
Mapping XS c12599e0
END DESCRIPTION:
XS GIS Cut Line= 3
      2889687.16     10226024.18      2890030.94     10225933.89
      2890249.70     10225659.57
#Sta/Elev= 30
  4642.3 1186.42  4661.2 1182.18  4671.8 1177.44  4706.8 1168.19  4713.1 1165.18
  4775.2 1147.54  4782.3 1143.79  4816.5 1133.91  4837.2 1126.65  4857.9 1121.34
  4868.2 1117.14  4903.4 1109.17  4909.6 1106.09  4938.6 1100.35  4950.9 1096.10
  4995.6 1085.85  4995.9 1085.35  4999.6 1085.85  5015.6 1086.18  5037.1 1088.57
  5044.5 1092.57  5050.9 1093.86  5058.9 1098.01  5079.7 1104.69  5114.9 1122.04
  5215.8 1161.00  5257.4 1179.38  5321.5 1195.91  5335.9 1199.03  5348.6 1200.10
#Mann=3,-1,0
  4642.3    0.12       0  4995.6    0.07       0  4999.6    0.12       0
Bank Sta=4995.6,4999.6
Exp/Cntr=0.3,0.1

Type RM Length L Ch R = 1,13500,500,500,500
BEGIN DESCRIPTION:
INKS 02 27.0
END DESCRIPTION:
XS GIS Cut Line= 3
      2889655.72     10226103.10      2890134.25     10226013.73
      2890255.68     10225803.13
#Sta/Elev= 30
  4513.2 1202.65  4597.2 1180.75  4644.8 1164.86  4649.9 1164.95  4665.8 1157.71
  4716.6 1143.27  4726.8 1138.60  4755.2 1129.93  4838.7 1107.62  4859.0 1105.68
  4865.7 1102.14  4879.4 1099.62  4970.9 1088.04  5003.2 1082.24  5015.5 1077.37
  5021.8 1077.35  5022.0 1076.85  5025.8 1077.35  5037.0 1078.22  5046.9 1081.59
  5058.6 1091.24  5104.6 1113.26  5117.4 1121.58  5127.5 1124.69  5139.2 1131.65
  5149.0 1134.99  5170.6 1146.04  5229.5 1167.99  5240.2 1173.24  5243.1 1173.24
#Mann=3,-1,0
  4513.2    0.12       0  5021.8    0.07       0  5025.8    0.12       0
Bank Sta=5021.8,5025.8
Exp/Cntr=0.3,0.1

Type RM Length L Ch R = 1,13000,500,500,500
BEGIN DESCRIPTION:
INKS 02 26.0
END DESCRIPTION:
XS GIS Cut Line= 3
      2890205.69     10226753.11      2890381.43     10226367.03
      2890505.67     10226003.15
#Sta/Elev= 30
  4575.8 1133.23  4636.2 1118.64  4659.2 1110.48  4718.6 1098.19  4728.4 1094.76
  4773.6 1086.46  4877.7 1076.66  4923.8 1066.05  4960.4 1063.67  4969.9 1065.08
  4996.5 1059.28  4996.7 1058.78  5000.5 1059.28  5014.7 1060.76  5024.3 1064.49
  5029.6 1063.25  5032.3 1064.77  5042.1 1068.94  5092.2 1083.51  5109.8 1086.38
  5130.9 1093.66  5141.5 1094.38  5194.3 1109.99  5204.9 1111.06  5226.0 1119.70
  5268.3 1132.10  5280.2 1138.23  5300.0 1143.22  5311.5 1148.36  5384.5 1170.29
#Mann=5,-1,0
  4575.8    0.12       0  4996.5    0.07       0  5000.5    0.12       0
  5032.3    0.05       0  5042.1    0.12       0
Bank Sta=4996.5,5000.5
Exp/Cntr=0.3,0.1

Type RM Length L Ch R = 1,12500,500,500,500
BEGIN DESCRIPTION:
INKS 02 25.0
END DESCRIPTION:
XS GIS Cut Line= 3
      2890655.70     10226953.07      2890840.98     10226542.66
      2890808.92     10226099.01
#Sta/Elev= 30
  4549.7 1133.04  4587.1 1128.20  4626.5 1118.71  4633.3 1115.73  4648.4 1113.97
  4692.3 1099.75  4806.2 1069.49  4857.9 1060.31  4899.4 1056.59  4983.6 1051.30
  4996.7 1047.58  4999.6 1045.31  5002.0 1045.31  5004.3 1047.58  5007.6 1044.48
  5007.8 1043.98  5011.6 1044.48  5069.7 1056.45  5129.9 1077.88  5138.9 1082.55
  5143.9 1081.33  5149.9 1085.19  5180.0 1097.03  5210.1 1106.12  5278.4 1120.40
  5283.4 1120.20  5350.5 1139.36  5370.5 1147.82  5390.6 1149.15  5444.8 1159.70
#Mann=5,-1,0
  4549.7    0.12       0  4899.4    0.05       0  4983.6    0.12       0
  5007.6    0.07       0  5011.6    0.12       0
Bank Sta=5007.6,5011.6
Exp/Cntr=0.3,0.1

Type RM Length L Ch R = 1,12000,500,500,500
BEGIN DESCRIPTION:
INKS 02 24.0
END DESCRIPTION:
XS GIS Cut Line= 3
      2890755.72     10227053.09      2891239.39     10226813.86
      2891505.65     10226753.12
#Sta/Elev= 30
  4460.4 1156.29  4513.7 1141.83  4527.3 1135.64  4571.9 1120.29  4616.5 1105.38
  4648.3 1097.00  4653.8 1093.96  4693.1 1086.57  4750.4 1071.23  4820.3 1056.83
  4855.7 1053.00  4906.6 1044.59  4944.8 1040.78  4973.6 1038.12  4984.7 1036.06
  4990.3 1033.55  5004.5 1033.22  5004.7 1032.72  5008.5 1033.22  5029.0 1037.80
  5088.5 1041.55  5109.0 1045.03  5120.1 1050.22  5129.9 1051.76  5158.0 1058.43
  5170.6 1064.86  5200.9 1073.28  5211.6 1080.14  5232.2 1087.75  5273.1 1102.93
#Mann=7,-1,0
  4460.4    0.12       0  4820.3    0.05       0  4944.8    0.12       0
  5004.5    0.07       0  5008.5    0.12       0  5129.9    0.05       0
  5232.2    0.12       0
Bank Sta=5004.5,5008.5
Exp/Cntr=0.3,0.1

Type RM Length L Ch R = 1,11500,500,500,500
BEGIN DESCRIPTION:
INKS 02 23.0
END DESCRIPTION:
XS GIS Cut Line= 3
      2891055.73     10227203.10      2891577.62     10227111.33
      2891655.69     10226903.08
#Sta/Elev= 30
  4470.1 1088.59  4490.4 1085.20  4497.2 1082.50  4502.3 1082.54  4591.9 1061.62
  4703.3 1046.43  4729.4 1042.37  4843.0 1031.31  4971.3 1025.36  4994.5 1024.02
  4994.7 1023.52  4998.5 1024.02  5006.1 1024.59  5030.1 1031.21  5041.7 1039.12
  5061.3 1045.16  5066.6 1050.49  5072.9 1054.34  5091.5 1061.05  5096.9 1066.10
  5115.6 1070.45  5127.1 1076.91  5146.7 1084.37  5158.3 1091.38  5177.0 1099.81
  5182.3 1105.10  5190.3 1109.51  5207.2 1113.81  5212.6 1117.04  5222.4 1118.66
#Mann=5,-1,0
  4470.1    0.12       0  4703.3    0.05       0  4971.3    0.12       0
  4994.5    0.07       0  4998.5    0.12       0
Bank Sta=4994.5,4998.5
Exp/Cntr=0.3,0.1

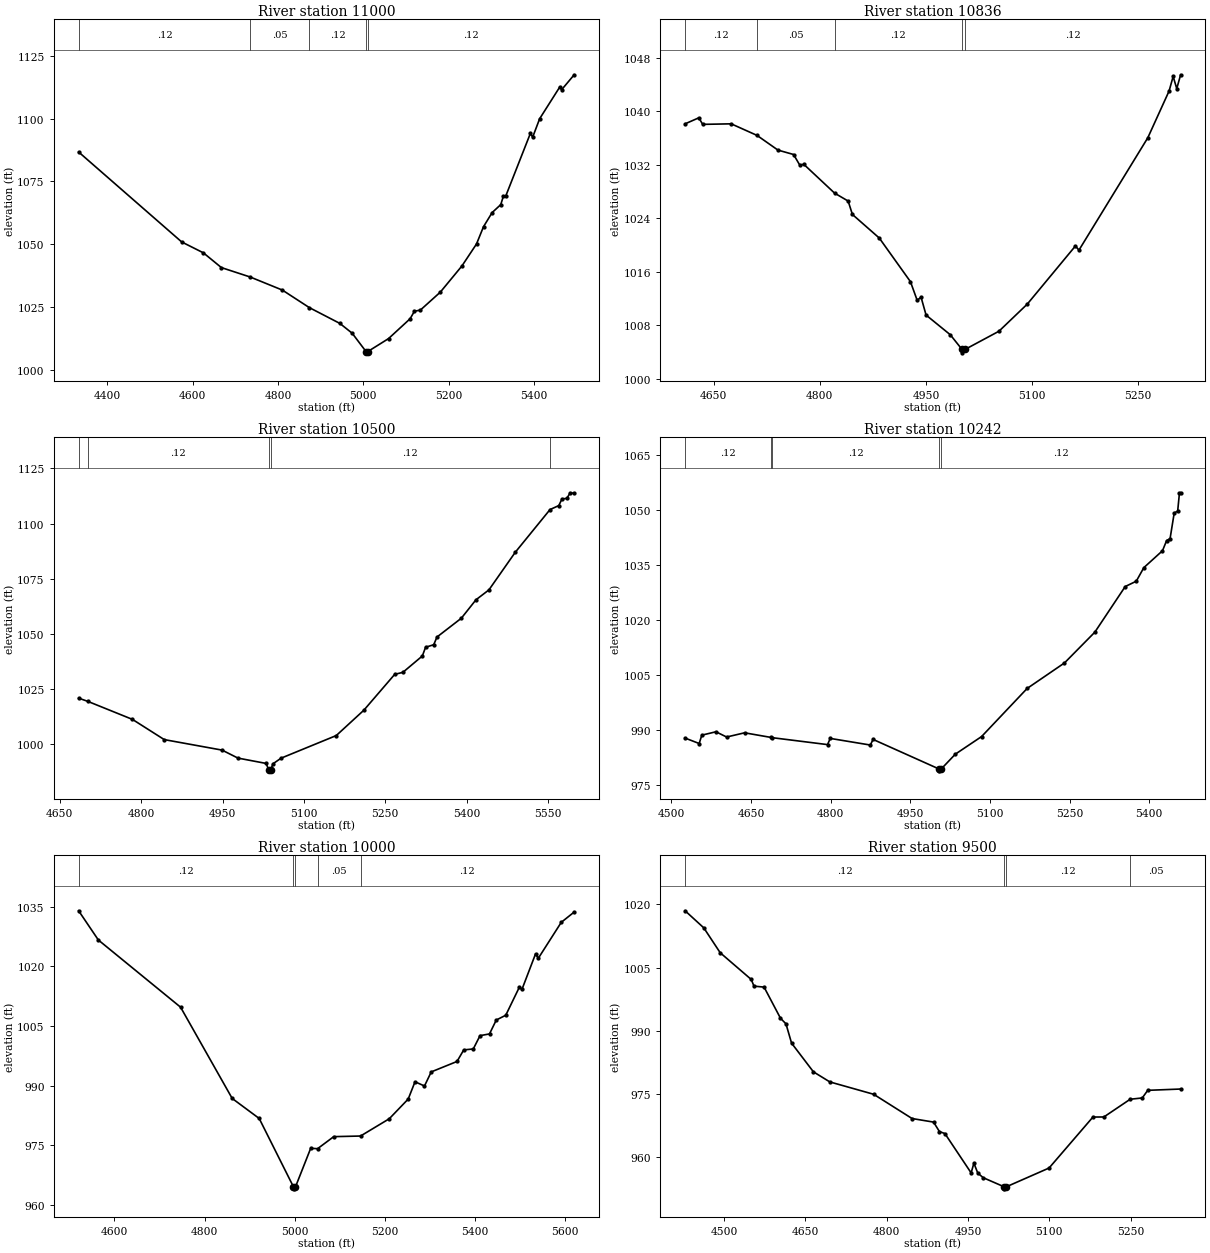
Type RM Length L Ch R = 1,11000,164,164,164
BEGIN DESCRIPTION:
INKS 02 22.0
END DESCRIPTION:
XS GIS Cut Line= 3
      2891255.69     10227903.11      2891780.52     10227491.30
      2891855.68     10227003.16
#Sta/Elev= 30
  4332.9 1086.73  4574.4 1050.91  4625.2 1046.58  4667.4 1040.70  4735.1 1036.94
  4810.2 1031.75  4873.5 1024.76  4944.9 1018.48  4973.8 1014.57  5006.3 1007.26
  5006.5 1006.76  5010.3 1007.26  5058.9 1012.42  5109.5 1020.33  5119.6 1023.32
  5133.6 1023.79  5180.3 1030.93  5230.9 1041.35  5265.1 1050.11  5281.5 1056.99
  5301.7 1062.61  5321.9 1065.78  5328.3 1069.28  5333.4 1069.11  5391.5 1094.23
  5396.6 1092.61  5413.0 1099.97  5459.8 1112.52  5464.9 1111.61  5493.9 1117.48
#Mann=5,-1,0
  4332.9    0.12       0  4735.1    0.05       0  4873.5    0.12       0
  5006.3    0.07       0  5010.3    0.12       0
Bank Sta=5006.3,5010.3
Exp/Cntr=0.3,0.1

Type RM Length L Ch R = 1,10836,336,336,336
BEGIN DESCRIPTION:
Mapping XS b42d0e6c
END DESCRIPTION:
XS GIS Cut Line= 3
      2891780.93     10227892.25      2891937.19     10227555.42
      2891961.40     10227226.83
#Sta/Elev= 30
  4609.4 1038.15  4628.8 1039.05  4634.3 1038.07  4674.6 1038.15  4711.1 1036.42
  4740.7 1034.22  4762.8 1033.56  4771.7 1031.95  4777.2 1032.10  4820.7 1027.79
  4840.0 1026.59  4846.0 1024.59  4884.0 1021.06  4928.1 1014.53  4937.6 1011.74
  4943.1 1012.21  4950.2 1009.53  4984.4 1006.59  5001.1 1004.38  5001.3 1003.88
  5005.1 1004.38  5053.2 1007.11  5093.3 1011.17  5161.4 1019.87  5166.4 1019.25
  5263.8 1036.07  5293.9 1043.07  5299.6 1045.24  5304.7 1043.42  5310.2 1045.49
#Mann=5,-1,0
  4609.4    0.12       0  4711.1    0.05       0  4820.7    0.12       0
  5001.1    0.07       0  5005.1    0.12       0
Bank Sta=5001.1,5005.1
Exp/Cntr=0.3,0.1

Type RM Length L Ch R = 1,10500,258,258,258
BEGIN DESCRIPTION:
INKS 02 21.0
END DESCRIPTION:
XS GIS Cut Line= 3
      2892055.71     10227703.08      2892241.66     10227448.32
      2891905.70     10226953.13
#Sta/Elev= 30
  4684.6 1020.85  4701.5 1019.39  4783.8 1011.22  4842.5 1002.05  4949.1  997.29
  4978.4  993.67  5030.5  991.24  5034.9  988.39  5035.2  987.89  5038.9  988.39
  5043.0  991.09  5057.9  993.63  5159.7 1003.89  5210.6 1015.39  5267.5 1031.65
  5282.5 1032.54  5318.4 1039.96  5324.4 1043.92  5339.4 1045.07  5345.4 1048.56
  5390.3 1057.08  5417.3 1065.44  5441.2 1069.93  5489.7 1086.96  5553.9 1106.36
  5570.0 1108.14  5576.0 1111.19  5584.9 1111.40  5591.0 1113.96  5598.4 1113.70
#Mann=5,-1,0
  4684.6    0.05       0  4701.5    0.12       0  5034.9    0.07       0
  5038.9    0.12       0  5553.9    0.12       0
Bank Sta=5034.9,5038.9
Exp/Cntr=0.3,0.1

Type RM Length L Ch R = 1,10242,242,242,242
BEGIN DESCRIPTION:
Mapping XS c5eefb30
END DESCRIPTION:
XS GIS Cut Line= 3
      2892534.42     10227770.74      2892478.86     10227326.25
      2892107.35     10227013.77
#Sta/Elev= 30
  4525.8  987.79  4552.3  986.31  4557.3  988.59  4583.9  989.51  4604.0  988.08
  4637.9  989.23  4687.6  987.97  4689.9  987.90  4794.1  986.01  4799.2  987.70
  4874.8  985.89  4879.8  987.43  5004.2  979.35  5004.5  978.85  5008.2  979.35
  5034.8  983.40  5084.3  988.21  5170.1 1001.34  5240.4 1008.30  5297.6 1016.70
  5354.8 1029.15  5375.6 1030.60  5389.9 1034.31  5425.0 1038.92  5432.8 1041.69
  5439.3 1042.23  5447.1 1049.24  5453.6 1049.72  5457.0 1054.74  5459.2 1054.74
#Mann=5,-1,0
  4525.8    0.12       0  4687.6    0.05       0  4689.9    0.12       0
  5004.2    0.07       0  5008.2    0.12       0
Bank Sta=5004.2,5008.2
Exp/Cntr=0.3,0.1

Type RM Length L Ch R = 1,10000,500,500,500
BEGIN DESCRIPTION:
INKS 02 20.0
END DESCRIPTION:
XS GIS Cut Line= 3
      2892844.50     10227743.96      2892671.20     10227296.98
      2892155.66     10226953.10
#Sta/Elev= 30
  4520.6 1033.94  4564.4 1026.59  4746.7 1009.72  4861.2  986.79  4921.1  981.76
  4997.1  964.58  4997.4  964.08  5001.6  964.58  5035.3  974.26  5050.6  974.17
  5086.4  977.19  5145.9  977.35  5209.6  981.69  5251.6  986.64  5266.7  990.98
  5287.7  989.92  5302.7  993.46  5359.8  996.08  5374.8  998.99  5395.9  999.22
  5410.9 1002.57  5431.9 1003.00  5446.9 1006.49  5468.0 1007.70  5498.0 1014.72
  5504.0 1014.22  5534.1 1023.13  5540.1 1022.00  5591.1 1031.04  5619.7 1033.62
#Mann=5,-1,0
  4520.6    0.12       0  4997.1    0.07       0  5001.6    0.12       0
  5050.6    0.05       0  5145.9    0.12       0
Bank Sta=4997.1,5001.6
Exp/Cntr=0.3,0.1

Type RM Length L Ch R = 1,9500,388,388,388
BEGIN DESCRIPTION:
INKS 02 19.0
END DESCRIPTION:
XS GIS Cut Line= 3
      2893022.46     10227657.22      2893106.79     10227091.47
      2893055.68     10226753.11
#Sta/Elev= 30
  4428.0 1018.48  4462.5 1014.42  4492.8 1008.50  4550.0 1002.16  4555.1 1000.57
  4573.7 1000.34  4604.0  992.94  4614.1  991.61  4624.4  987.03  4664.7  980.21
  4695.0  977.81  4775.9  974.87  4846.7  969.11  4886.4  968.26  4897.2  966.01
  4907.3  965.54  4955.7  956.19  4960.8  958.50  4968.0  956.13  4978.1  955.04
  5016.3  952.90  5016.6  952.40  5020.9  952.90  5099.5  957.35  5180.4  969.46
  5200.6  969.48  5249.1  973.69  5271.4  974.00  5281.5  975.81  5342.2  976.12
#Mann=4,-1,0
  4428.0    0.12       0  5016.3    0.07       0  5020.9    0.12       0
  5249.1    0.05       0
Bank Sta=5016.3,5020.9
Exp/Cntr=0.3,0.1

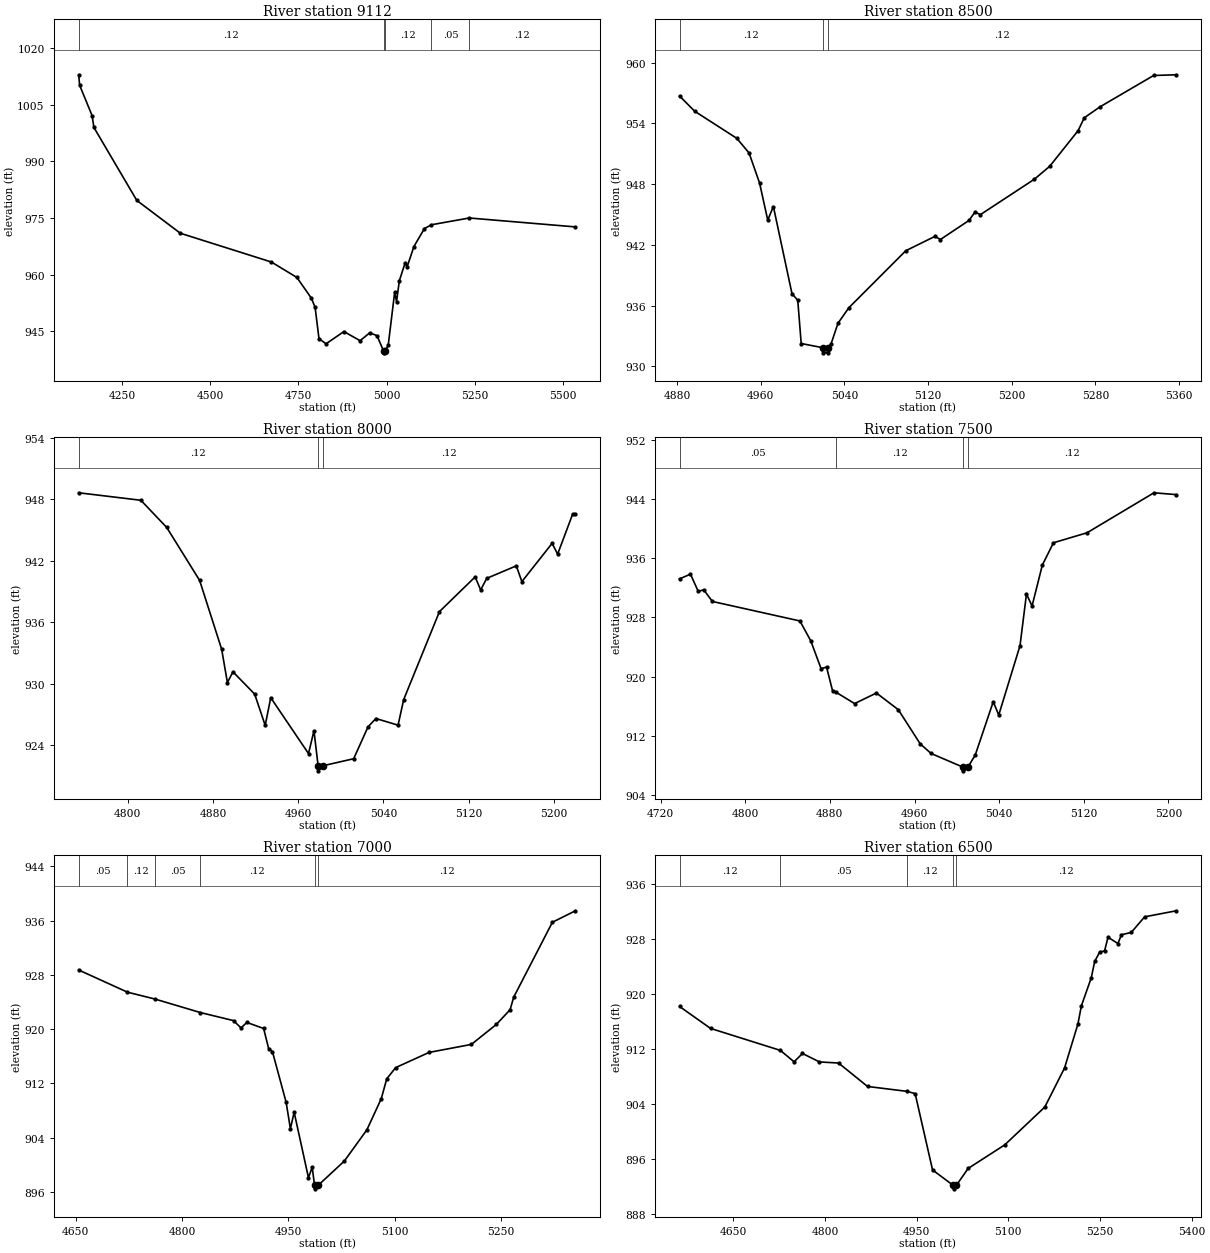
Type RM Length L Ch R = 1,9112,612,612,612
BEGIN DESCRIPTION:
INKS 02 18.0
END DESCRIPTION:
XS GIS Cut Line= 3
      2893200.41     10227822.14      2893420.00     10226977.00
      2893226.75     10226477.37
#Sta/Elev= 30
  4126.8 1012.96  4129.4 1010.20  4164.8 1002.15  4170.0  998.99  4291.6  979.66
  4415.1  970.96  4673.4  963.33  4745.7  959.24  4787.0  953.71  4797.4  951.29
  4808.4  943.00  4828.4  941.66  4879.1  944.90  4924.9  942.48  4952.4  944.57
  4973.0  943.81  4991.4  939.76  4991.7  939.26  4996.0  939.76  5004.8  941.30
  5023.0  955.28  5028.4  952.85  5036.3  958.39  5053.0  963.17  5058.3  962.02
  5077.6  967.43  5107.5  972.21  5127.5  973.21  5234.6  975.00  5535.7  972.64
#Mann=5,-1,0
  4126.8    0.12       0  4991.4    0.07       0  4996.0    0.12       0
  5127.5    0.05       0  5234.6    0.12       0
Bank Sta=4991.4,4996
Exp/Cntr=0.3,0.1

Type RM Length L Ch R = 1,8500,500,500,500
BEGIN DESCRIPTION:
INKS 02 17.0
END DESCRIPTION:
XS GIS Cut Line= 3
      2893655.69     10227453.10      2893703.30     10227345.46
      2893805.67     10227003.14
#Sta/Elev= 30
  4882.3  956.71  4896.7  955.21  4937.0  952.53  4948.7  951.09  4958.8  948.11
  4966.6  944.45  4972.0  945.79  4989.8  937.17  4995.3  936.53  4998.6  932.25
  5019.6  931.83  5019.9  931.33  5023.9  931.33  5024.2  931.83  5027.2  932.23
  5033.8  934.26  5044.2  935.79  5098.6  941.42  5126.5  942.84  5131.7  942.53
  5159.0  944.41  5164.8  945.24  5170.0  944.99  5221.6  948.49  5236.2  949.76
  5263.4  953.29  5269.3  954.56  5284.3  955.64  5335.6  958.74  5357.3  958.81
#Mann=3,-1,0
  4882.3    0.12       0  5019.6    0.07       0  5024.2    0.12       0
Bank Sta=5019.6,5024.2
Exp/Cntr=0.3,0.1

Type RM Length L Ch R = 1,8000,500,500,500
BEGIN DESCRIPTION:
INKS 02 16.0
END DESCRIPTION:
XS GIS Cut Line= 3
      2894105.68     10227503.14      2894167.24     10227264.76
      2894105.69     10227053.13
#Sta/Elev= 30
  4753.8  948.62  4812.2  947.89  4836.5  945.24  4867.4  940.08  4888.1  933.37
  4893.5  930.12  4898.7  931.17  4919.1  929.00  4929.0  925.95  4934.2  928.65
  4969.7  923.20  4974.8  925.43  4978.7  922.02  4979.0  921.52  4983.4  922.02
  5012.1  922.70  5025.6  925.81  5033.0  926.62  5053.8  925.97  5059.1  928.47
  5092.7  937.04  5126.2  940.42  5131.4  939.15  5137.1  940.28  5164.9  941.50
  5170.1  939.96  5198.5  943.69  5203.7  942.64  5217.8  946.54  5220.4  946.54
#Mann=3,-1,0
  4753.8    0.12       0  4978.7    0.07       0  4983.4    0.12       0
Bank Sta=4978.7,4983.4
Exp/Cntr=0.3,0.1

Type RM Length L Ch R = 1,7500,500,500,500
BEGIN DESCRIPTION:
INKS 02 15.0
END DESCRIPTION:
XS GIS Cut Line= 3
      2894555.69     10227553.10      2894622.02     10227299.63
      2894555.69     10227103.12
#Sta/Elev= 30
  4738.0  933.23  4748.3  933.87  4755.6  931.54  4760.8  931.75  4769.0  930.17
  4851.7  927.53  4862.0  924.83  4871.7  921.07  4876.9  921.27  4882.7  918.00
  4886.1  917.85  4903.4  916.34  4924.0  917.77  4944.7  915.51  4965.4  910.88
  4975.7  909.58  5005.8  907.73  5006.2  907.23  5010.5  907.73  5017.4  909.37
  5034.4  916.59  5039.6  914.79  5059.7  924.18  5065.8  931.18  5071.1  929.56
  5080.8  935.10  5091.3  938.12  5123.0  939.47  5186.3  944.89  5207.4  944.64
#Mann=4,-1,0
  4738.0    0.05       0  4886.1    0.12       0  5005.8    0.07       0
  5010.5    0.12       0
Bank Sta=5005.8,5010.5
Exp/Cntr=0.3,0.1

Type RM Length L Ch R = 1,7000,500,500,500
BEGIN DESCRIPTION:
INKS 02 14.0
END DESCRIPTION:
XS GIS Cut Line= 3
      2894949.55     10227678.86      2895066.31     10227353.26
      2895005.68     10227003.07
#Sta/Elev= 30
  4654.1  928.72  4723.0  925.45  4761.7  924.44  4825.8  922.45  4872.7  921.26
  4883.3  920.18  4891.5  920.99  4915.2  920.10  4922.3  917.13  4927.6  916.70
  4947.0  909.21  4953.0  905.32  4958.3  907.75  4978.5  898.10  4983.8  899.65
  4987.1  896.96  4987.4  896.46  4992.0  896.96  5029.2  900.56  5061.0  905.16
  5081.3  909.75  5089.0  912.67  5101.6  914.33  5148.8  916.57  5208.5  917.75
  5243.7  920.69  5263.2  922.87  5268.3  924.72  5322.9  935.76  5355.4  937.45
#Mann=6,-1,0
  4654.1    0.05       0  4723.0    0.12       0  4761.7    0.05       0
  4825.8    0.12       0  4987.1    0.07       0  4992.0    0.12       0
Bank Sta=4987.1,4992
Exp/Cntr=0.3,0.1

Type RM Length L Ch R = 1,6500,500,500,500
BEGIN DESCRIPTION:
INKS 02 13.0
END DESCRIPTION:
XS GIS Cut Line= 3
      2895655.69     10227603.12      2895534.87     10227182.22
      2895205.65     10227003.09
#Sta/Elev= 30
  4562.1  918.19  4612.7  915.00  4727.0  911.80  4749.4  910.14  4763.2  911.35
  4791.0  910.12  4822.2  909.96  4869.6  906.55  4934.0  905.84  4947.5  905.51
  4976.0  894.40  5009.9  892.15  5010.3  891.65  5014.9  892.15  5034.2  894.62
  5094.1  898.05  5159.6  903.55  5191.9  909.23  5213.8  915.63  5219.4  918.26
  5235.6  922.35  5241.3  924.76  5249.5  926.12  5257.4  926.28  5263.1  928.27
  5279.3  927.35  5285.0  928.63  5301.1  928.97  5323.0  931.24  5374.8  932.12
#Mann=5,-1,0
  4562.1    0.12       0  4727.0    0.05       0  4934.0    0.12       0
  5009.9    0.07       0  5014.9    0.12       0
Bank Sta=5009.9,5014.9
Exp/Cntr=0.3,0.1