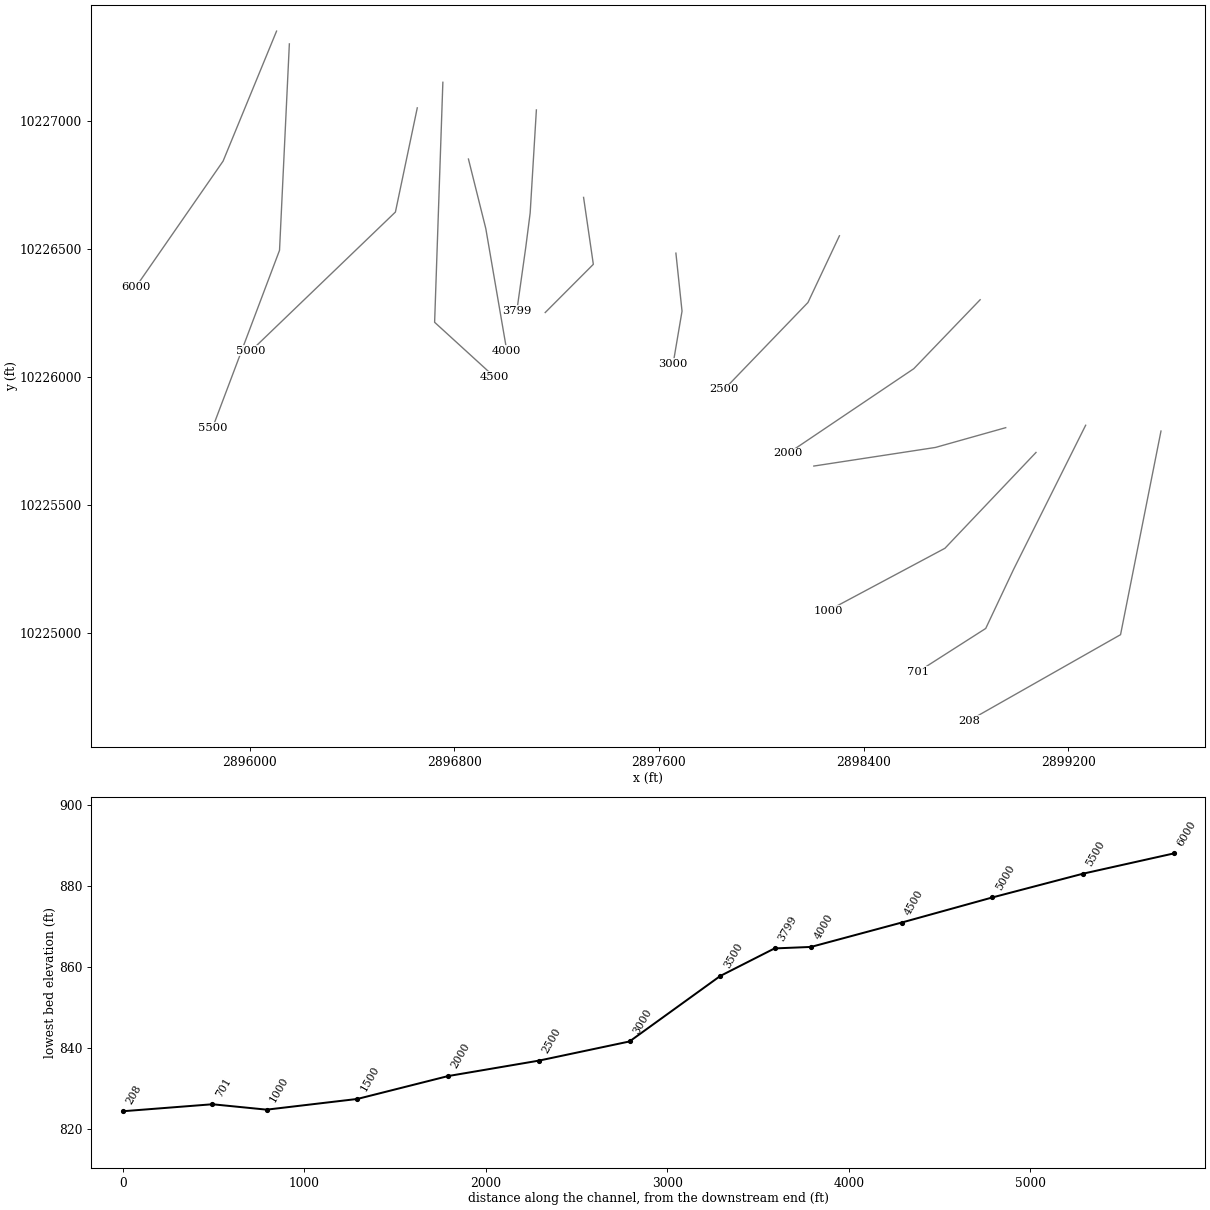
HEC-RAS study INKS 02.prj: INKS 02 Base Level Engineering

--- INKS 02.g01 (geometry) --- (continued)

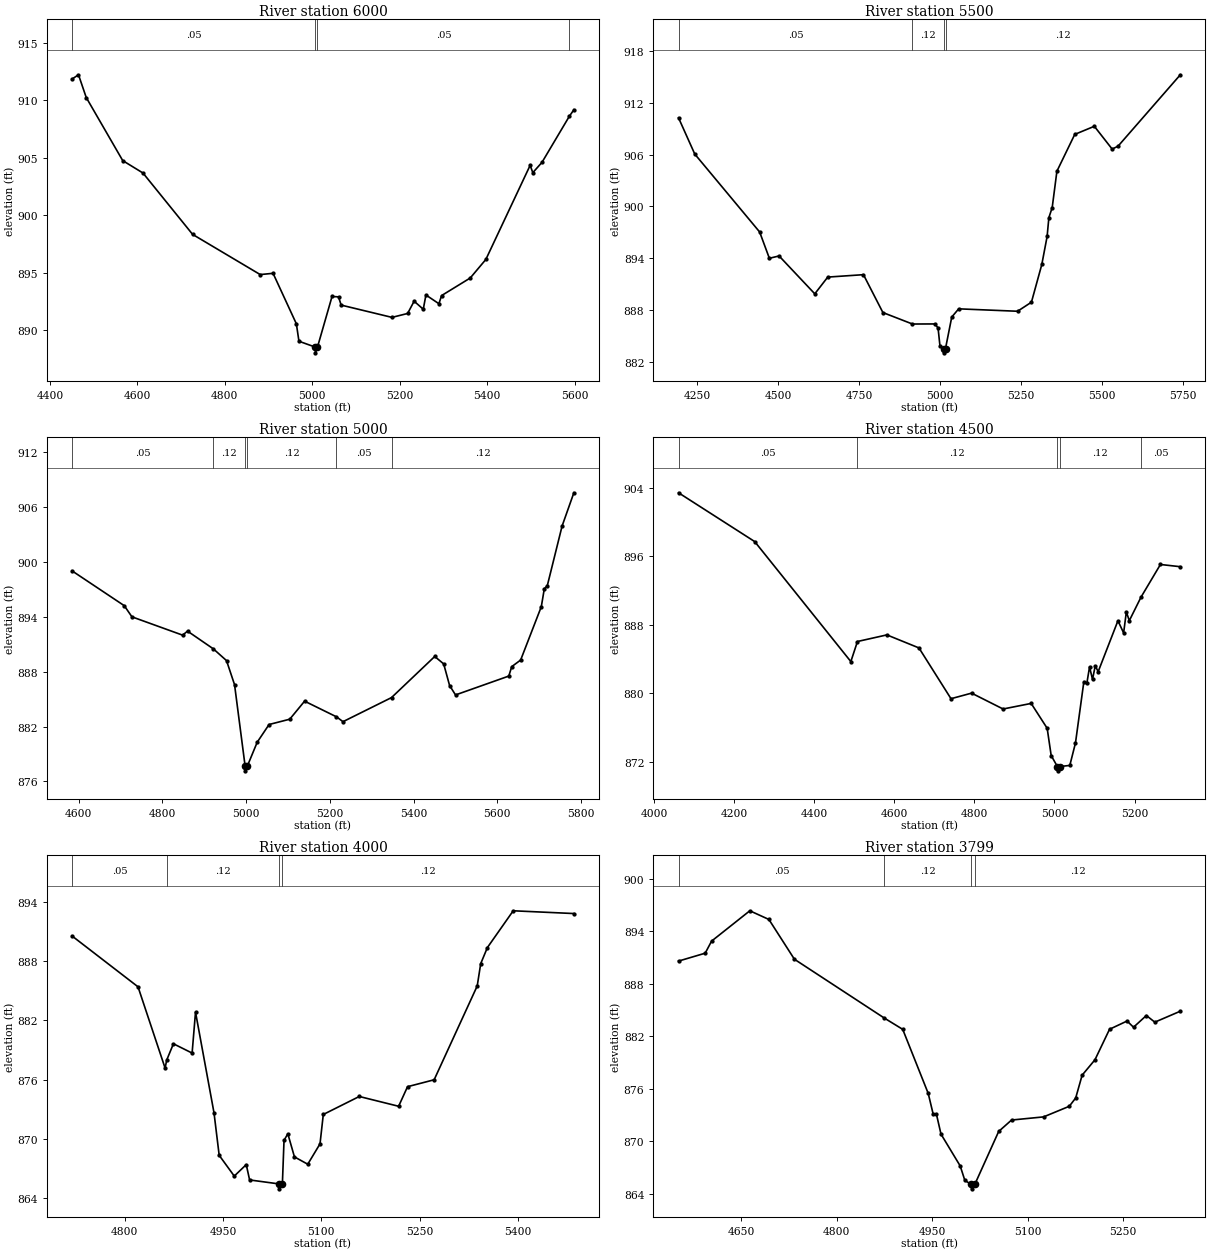
Type RM Length L Ch R = 1,6000,500,500,500
BEGIN DESCRIPTION:
INKS 02 12.0
END DESCRIPTION:
XS GIS Cut Line= 3
      2896105.67     10227353.08      2895896.64     10226844.90
      2895555.69     10226353.12
#Sta/Elev= 30
  4450.5  911.87  4465.2  912.24  4482.9  910.26  4566.4  904.76  4612.7  903.68
  4726.3  898.33  4880.9  894.83  4910.3  894.94  4963.6  890.54  4969.5  889.02
  5006.9  888.51  5007.3  888.01  5011.9  888.51  5045.2  892.92  5060.0  892.89
  5066.1  892.17  5182.3  891.10  5218.1  891.44  5233.0  892.51  5253.9  891.81
  5260.0  893.05  5289.7  892.29  5295.8  893.00  5361.3  894.53  5397.1  896.15
  5498.4  904.35  5504.5  903.71  5525.5  904.61  5588.0  908.62  5598.4  909.19
#Mann=4,-1,0
  4450.5    0.05       0  5006.9    0.03       0  5011.9    0.05       0
  5588.0    0.12       0
Bank Sta=5006.9,5011.9
Exp/Cntr=0.3,0.1

Type RM Length L Ch R = 1,5500,500,500,500
BEGIN DESCRIPTION:
INKS 02 11.0
END DESCRIPTION:
XS GIS Cut Line= 3
      2896155.69     10227303.14      2896117.26     10226496.35
      2895855.70     10225803.16
#Sta/Elev= 30
  4192.3  910.26  4242.4  906.06  4442.6  897.03  4472.6  893.98  4502.6  894.25
  4612.8  889.86  4652.8  891.80  4763.0  892.08  4823.0  887.69  4914.2  886.36
  4983.2  886.37  4993.2  885.91  4999.1  883.82  5011.2  883.52  5011.6  883.02
  5016.2  883.52  5035.5  887.17  5056.9  888.12  5238.6  887.84  5281.4  888.89
  5313.4  893.26  5329.8  896.51  5335.2  898.69  5345.5  899.86  5360.0  904.07
  5415.1  908.34  5475.5  909.28  5530.5  906.64  5548.6  906.97  5740.9  915.25
#Mann=4,-1,0
  4192.3    0.05       0  4914.2    0.12       0  5011.2    0.07       0
  5016.2    0.12       0
Bank Sta=5011.2,5016.2
Exp/Cntr=0.3,0.1

Type RM Length L Ch R = 1,5000,500,500,500
BEGIN DESCRIPTION:
INKS 02 10.0
END DESCRIPTION:
XS GIS Cut Line= 3
      2896655.69     10227053.12      2896570.23     10226645.89
      2896005.72     10226103.14
#Sta/Elev= 30
  4583.9  899.00  4708.6  895.20  4727.0  893.98  4848.1  891.98  4859.8  892.42
  4921.6  890.48  4953.0  889.20  4972.2  886.57  4997.5  877.66  4997.9  877.16
  5002.6  877.66  5026.4  880.29  5054.7  882.22  5104.1  882.80  5139.6  884.77
  5215.8  883.06  5231.4  882.53  5347.3  885.16  5450.6  889.65  5472.0  888.84
  5486.1  886.48  5500.3  885.45  5627.6  887.51  5634.6  888.54  5655.9  889.26
  5705.3  895.09  5712.5  897.05  5719.5  897.36  5755.0  903.90  5783.1  907.53
#Mann=6,-1,0
  4583.9    0.05       0  4921.6    0.12       0  4997.5    0.07       0
  5002.6    0.12       0  5215.8    0.05       0  5347.3    0.12       0
Bank Sta=4997.5,5002.6
Exp/Cntr=0.3,0.1

Type RM Length L Ch R = 1,4500,500,500,500
BEGIN DESCRIPTION:
INKS 02 9.0
END DESCRIPTION:
XS GIS Cut Line= 3
      2896755.69     10227153.15      2896723.46     10226215.01
      2896955.71     10226003.09
#Sta/Elev= 30
  4061.3  903.39  4251.5  897.70  4491.6  883.71  4508.1  886.05  4581.6  886.82
  4661.7  885.30  4741.7  879.38  4793.1  880.03  4871.8  878.18  4941.9  878.83
  4981.9  875.93  4991.9  872.75  5007.4  871.47  5007.8  870.97  5012.7  871.47
  5038.4  871.60  5052.6  874.23  5073.5  881.37  5080.9  881.16  5087.7  883.09
  5095.1  881.63  5101.9  883.20  5109.3  882.54  5158.6  888.47  5172.8  887.05
  5179.6  889.50  5187.0  888.48  5216.2  891.22  5264.7  895.03  5314.4  894.77
#Mann=5,-1,0
  4061.3    0.05       0  4508.1    0.12       0  5007.4    0.07       0
  5012.7    0.12       0  5216.2    0.05       0
Bank Sta=5007.4,5012.7
Exp/Cntr=0.3,0.1

Type RM Length L Ch R = 1,4000,201,201,201
BEGIN DESCRIPTION:
INKS 02 8.0
END DESCRIPTION:
XS GIS Cut Line= 3
      2896855.68     10226853.13      2896923.51     10226581.27
      2897005.69     10226103.08
#Sta/Elev= 30
  4719.8  890.53  4820.4  885.39  4861.7  877.17  4864.2  877.99  4874.4  879.63
  4902.9  878.69  4908.1  882.83  4936.3  872.65  4944.2  868.35  4967.2  866.25
  4985.5  867.41  4990.6  865.86  5035.3  865.46  5035.7  864.96  5040.6  865.46
  5043.1  869.86  5048.9  870.53  5059.0  868.19  5079.3  867.45  5098.0  869.51
  5103.0  872.48  5157.9  874.30  5217.9  873.31  5231.5  875.29  5272.1  875.99
  5337.8  885.48  5343.1  887.73  5353.3  889.36  5392.7  893.08  5485.2  892.80
#Mann=4,-1,0
  4719.8    0.05       0  4864.2    0.12       0  5035.3    0.07       0
  5040.6    0.12       0
Bank Sta=5035.3,5040.6
Exp/Cntr=0.3,0.1

Type RM Length L Ch R = 1,3799,299,299,299
BEGIN DESCRIPTION:
Mapping XS 18515ea5
END DESCRIPTION:
XS GIS Cut Line= 4
      2897121.22     10227044.97      2897096.91     10226642.22
      2897079.55     10226506.81      2897044.83     10226260.25
#Sta/Elev= 30
  4551.2  890.58  4593.1  891.48  4603.2  892.86  4663.3  896.32  4693.3  895.33
  4733.4  890.79  4874.7  884.08  4903.7  882.79  4943.8  875.48  4951.7  873.08
  4956.8  873.08  4963.9  870.83  4994.1  867.20  5001.4  865.55  5011.6  865.09
  5012.0  864.59  5017.0  865.09  5054.6  871.14  5074.8  872.44  5125.2  872.80
  5165.6  874.01  5175.7  874.96  5185.8  877.56  5206.0  879.32  5228.9  882.80
  5256.5  883.74  5266.6  883.03  5286.8  884.37  5300.1  883.61  5340.2  884.86
#Mann=4,-1,0
  4551.2    0.05       0  4874.7    0.12       0  5011.6    0.07       0
  5017.0    0.12       0
Bank Sta=5011.6,5017
Exp/Cntr=0.3,0.1

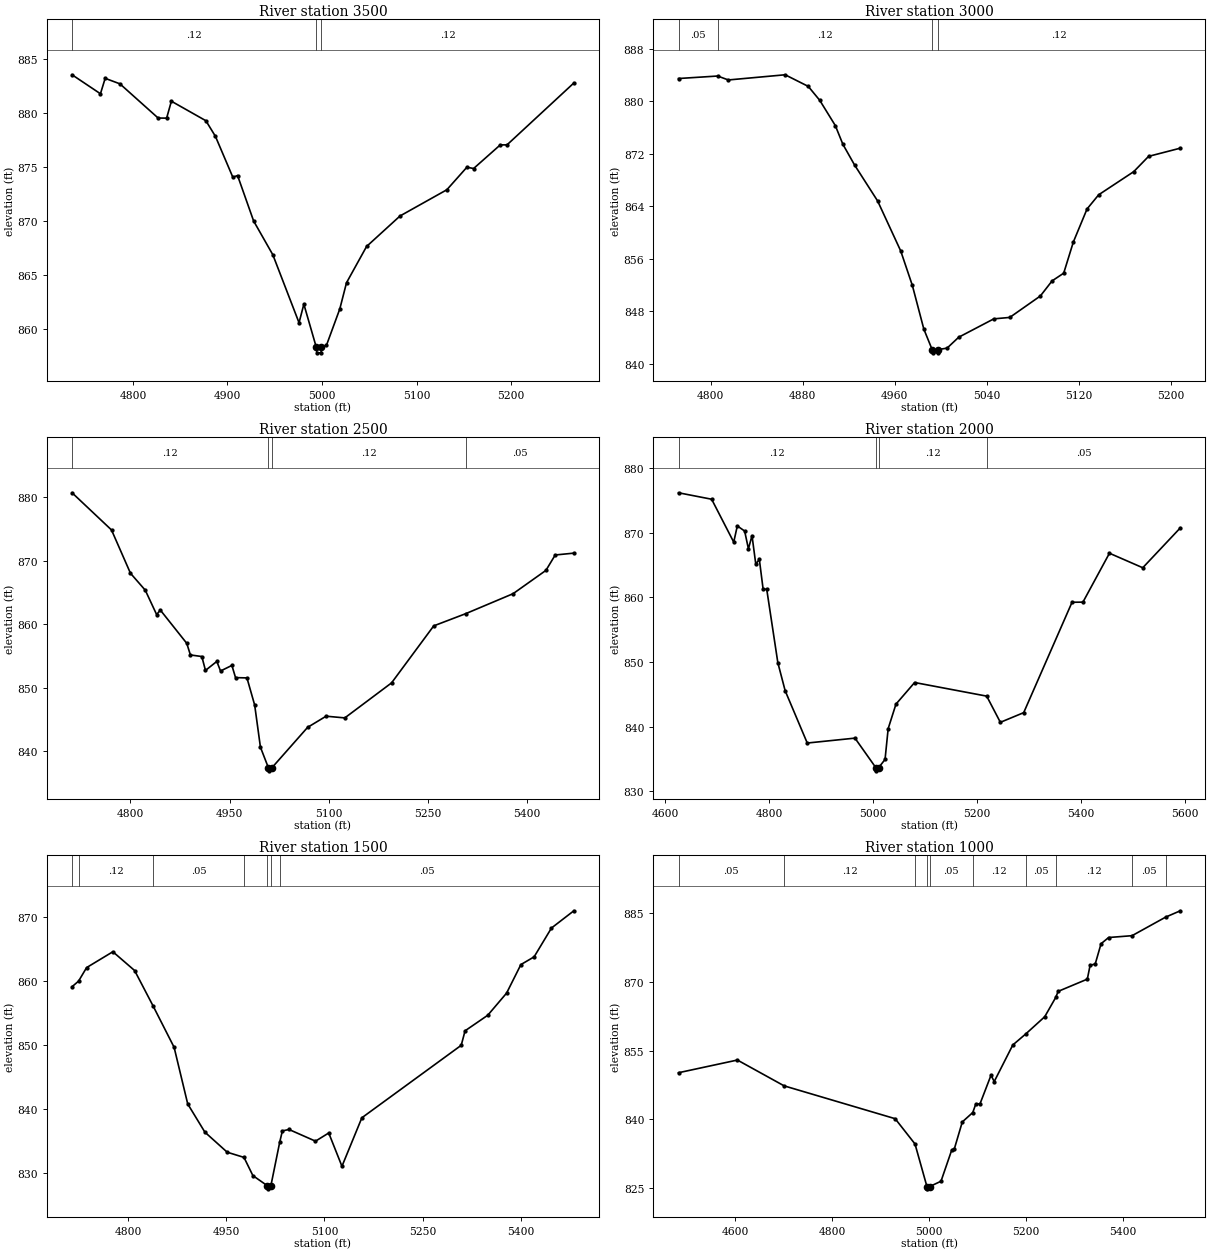
Type RM Length L Ch R = 1,3500,500,500,500
BEGIN DESCRIPTION:
INKS 02 7.0
END DESCRIPTION:
XS GIS Cut Line= 3
      2897305.68     10226703.14      2897343.83     10226441.61
      2897155.71     10226253.13
#Sta/Elev= 30
  4735.7  883.58  4765.7  881.82  4770.7  883.25  4786.3  882.74  4826.7  879.57
  4835.7  879.56  4840.7  881.13  4877.2  879.32  4887.3  877.87  4905.7  874.08
  4910.7  874.24  4927.7  870.02  4948.0  866.89  4975.7  860.59  4980.8  862.31
  4994.0  858.30  4994.5  857.80  4999.0  857.80  4999.4  858.30  5004.7  858.50
  5018.8  861.87  5025.9  864.30  5047.1  867.66  5082.5  870.49  5132.0  872.92
  5153.2  875.01  5160.3  874.89  5188.5  877.08  5195.6  877.08  5266.3  882.82
#Mann=3,-1,0
  4735.7    0.12       0  4994.0    0.07       0  4999.4    0.12       0
Bank Sta=4994,4999.4
Exp/Cntr=0.3,0.1

Type RM Length L Ch R = 1,3000,500,500,500
BEGIN DESCRIPTION:
INKS 02 6.0
END DESCRIPTION:
XS GIS Cut Line= 3
      2897666.56     10226485.27      2897690.49     10226258.43
      2897655.69     10226053.16
#Sta/Elev= 30
  4771.9  883.49  4805.9  883.87  4815.2  883.27  4864.6  884.06  4884.7  882.29
  4894.7  880.16  4908.2  876.32  4914.8  873.46  4924.9  870.32  4945.0  864.82
  4965.1  857.19  4975.2  851.94  4985.2  845.27  4992.4  842.16  4992.8  841.66
  4997.4  841.66  4997.8  842.16  5005.4  842.38  5015.5  844.04  5046.0  846.84
  5059.9  847.06  5086.5  850.33  5096.7  852.63  5106.8  853.81  5115.2  858.57
  5127.1  863.60  5137.2  865.76  5167.7  869.29  5180.6  871.62  5208.2  872.87
#Mann=4,-1,0
  4771.9    0.05       0  4805.9    0.12       0  4992.4    0.07       0
  4997.8    0.12       0
Bank Sta=4992.4,4997.8
Exp/Cntr=0.3,0.1

Type RM Length L Ch R = 1,2500,500,500,500
BEGIN DESCRIPTION:
INKS 02 5.0
END DESCRIPTION:
XS GIS Cut Line= 3
      2898305.68     10226553.10      2898182.70     10226292.35
      2897855.68     10225953.10
#Sta/Elev= 30
  4711.7  880.74  4771.4  874.88  4800.1  868.06  4822.5  865.39  4839.7  861.55
  4845.3  862.26  4885.3  857.02  4890.8  855.19  4908.1  854.94  4913.6  852.75
  4930.8  854.17  4936.4  852.66  4953.6  853.54  4959.1  851.62  4976.4  851.57
  4988.1  847.29  4996.8  840.66  5008.8  837.43  5009.3  836.93  5014.3  837.43
  5068.2  843.78  5096.2  845.54  5124.5  845.27  5195.3  850.79  5259.1  859.77
  5307.2  861.68  5379.2  864.84  5428.9  868.51  5443.0  870.94  5471.2  871.23
#Mann=4,-1,0
  4711.7    0.12       0  5008.8    0.07       0  5014.3    0.12       0
  5307.2    0.05       0
Bank Sta=5008.8,5014.3
Exp/Cntr=0.3,0.1

Type RM Length L Ch R = 1,2000,500,500,500
BEGIN DESCRIPTION:
INKS 02 4.0
END DESCRIPTION:
XS GIS Cut Line= 3
      2898855.70     10226303.13      2898596.39     10226033.63
      2898105.72     10225703.13
#Sta/Elev= 30
  4626.0  876.23  4689.7  875.23  4732.2  868.58  4739.1  871.09  4753.2  870.30
  4760.5  867.54  4767.4  869.59  4774.6  865.19  4781.5  865.90  4788.8  861.27
  4795.7  861.28  4817.1  849.89  4831.2  845.54  4873.7  837.44  4965.5  838.20
  5005.6  833.63  5006.1  833.13  5011.1  833.63  5023.4  834.90  5029.4  839.67
  5044.4  843.47  5080.3  846.82  5219.0  844.71  5245.3  840.65  5290.2  842.15
  5383.2  859.26  5404.2  859.28  5455.2  866.86  5519.3  864.61  5591.6  870.79
#Mann=4,-1,0
  4626.0    0.12       0  5005.6    0.07       0  5011.1    0.12       0
  5219.0    0.05       0
Bank Sta=5005.6,5011.1
Exp/Cntr=0.3,0.1

Type RM Length L Ch R = 1,1500,500,500,500
BEGIN DESCRIPTION:
INKS 02 3.0
END DESCRIPTION:
XS GIS Cut Line= 3
      2898955.68     10225803.11      2898680.94     10225725.82
      2898205.67     10225653.11
#Sta/Elev= 30
  4714.6  859.12  4724.5  859.99  4736.8  862.11  4776.9  864.59  4810.1  861.65
  4838.3  856.11  4870.4  849.64  4891.2  840.77  4917.4  836.36  4951.5  833.22
  4977.1  832.41  4990.7  829.56  5012.6  827.99  5013.1  827.49  5018.2  827.99
  5031.8  834.86  5035.7  836.55  5045.8  836.78  5086.3  834.95  5106.5  836.23
  5126.7  831.02  5157.1  838.61  5308.8  849.95  5314.7  852.22  5349.3  854.65
  5378.1  858.12  5399.9  862.58  5420.1  863.79  5446.6  868.30  5480.8  871.00
#Mann=7,-1,0
  4714.6    0.05       0  4724.5    0.12       0  4838.3    0.05       0
  4977.1    0.12       0  5012.6    0.07       0  5018.2    0.12       0
  5031.8    0.05       0
Bank Sta=5012.6,5018.2
Exp/Cntr=0.3,0.1

Type RM Length L Ch R = 1,1000,299,299,299
BEGIN DESCRIPTION:
INKS 02 2.0
END DESCRIPTION:
XS GIS Cut Line= 3
      2899074.05     10225706.22      2898718.10     10225331.69
      2898261.50     10225087.91
#Sta/Elev= 30
  4483.3  850.21  4604.6  852.98  4701.0  847.34  4929.8  840.17  4970.7  834.65
  4995.3  825.35  4995.8  824.85  5000.9  825.35  5024.3  826.51  5046.2  833.26
  5051.9  833.62  5068.2  839.46  5089.8  841.52  5095.8  843.32  5104.8  843.44
  5127.4  849.66  5134.0  848.28  5172.3  856.27  5199.2  858.70  5238.1  862.44
  5260.7  866.64  5265.8  867.98  5325.9  870.65  5331.6  873.66  5342.2  873.97
  5354.2  878.38  5369.8  879.74  5418.1  880.14  5487.4  884.20  5517.6  885.58
#Mann=10,-1,0
  4483.3    0.05       0  4701.0    0.12       0  4970.7    0.05       0
  4995.3    0.03       0  5000.9    0.05       0  5089.8    0.12       0
  5199.2    0.05       0  5260.7    0.12       0  5418.1    0.05       0
  5487.4    0.12       0
Bank Sta=4995.3,5000.9
Exp/Cntr=0.3,0.1

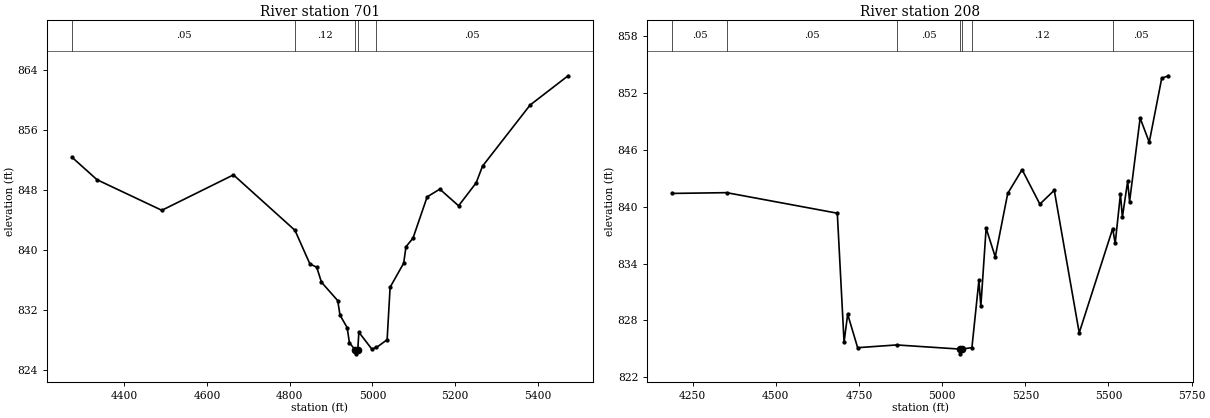
Type RM Length L Ch R = 1,701,493,493,493
BEGIN DESCRIPTION:
Mapping XS 9292f8bd
END DESCRIPTION:
XS GIS Cut Line= 4
      2899268.12     10225812.56      2898986.01     10225248.32
      2898877.50     10225018.29      2898612.75     10224849.03
#Sta/Elev= 30
  4273.3  852.39  4334.4  849.37  4490.9  845.30  4664.0  850.02  4812.7  842.63
  4848.7  838.16  4865.2  837.72  4876.7  835.72  4916.0  833.27  4921.5  831.34
  4938.8  829.67  4944.3  827.65  4958.7  826.68  4959.2  826.18  4964.4  826.68
  4967.1  829.06  4998.3  826.82  5009.7  827.03  5035.4  828.06  5042.6  835.05
  5075.4  838.26  5081.0  840.45  5097.9  841.59  5132.1  847.09  5162.7  848.12
  5208.1  845.90  5250.6  848.96  5265.9  851.18  5380.9  859.32  5472.7  863.22
#Mann=5,-1,0
  4273.3    0.05       0  4812.7    0.12       0  4958.7    0.07       0
  4964.4    0.12       0  5009.7    0.05       0
Bank Sta=4958.7,4964.4
Exp/Cntr=0.3,0.1

Type RM Length L Ch R = 1,208,0,0,0
BEGIN DESCRIPTION:
INKS 02 1.0
END DESCRIPTION:
XS GIS Cut Line= 3
      2899562.55     10225789.86      2899404.50     10224994.00
      2898812.86     10224658.19
#Sta/Elev= 30
  4188.6  841.41  4352.2  841.49  4684.9  839.32  4705.2  825.69  4716.0  828.65
  4746.0  825.11  4863.3  825.40  5054.3  824.96  5054.8  824.46  5060.1  824.96
  5089.5  825.12  5110.5  832.21  5116.3  829.50  5132.2  837.73  5159.6  834.71
  5197.1  841.41  5240.3  843.92  5293.7  840.28  5337.0  841.74  5412.0  826.68
  5512.7  837.70  5520.1  836.12  5536.0  841.34  5541.7  838.90  5557.6  842.69
  5563.4  840.55  5595.1  849.37  5622.5  846.82  5660.0  853.58  5680.3  853.84
#Mann=7,-1,0
  4188.6    0.05       0  4352.2    0.05       0  4863.3    0.05       0
  5054.3    0.03       0  5060.1    0.05       0  5089.5    0.12       0
  5512.7    0.05       0
Bank Sta=5054.3,5060.1
Exp/Cntr=0.3,0.1

Chan Stop Cuts=-1