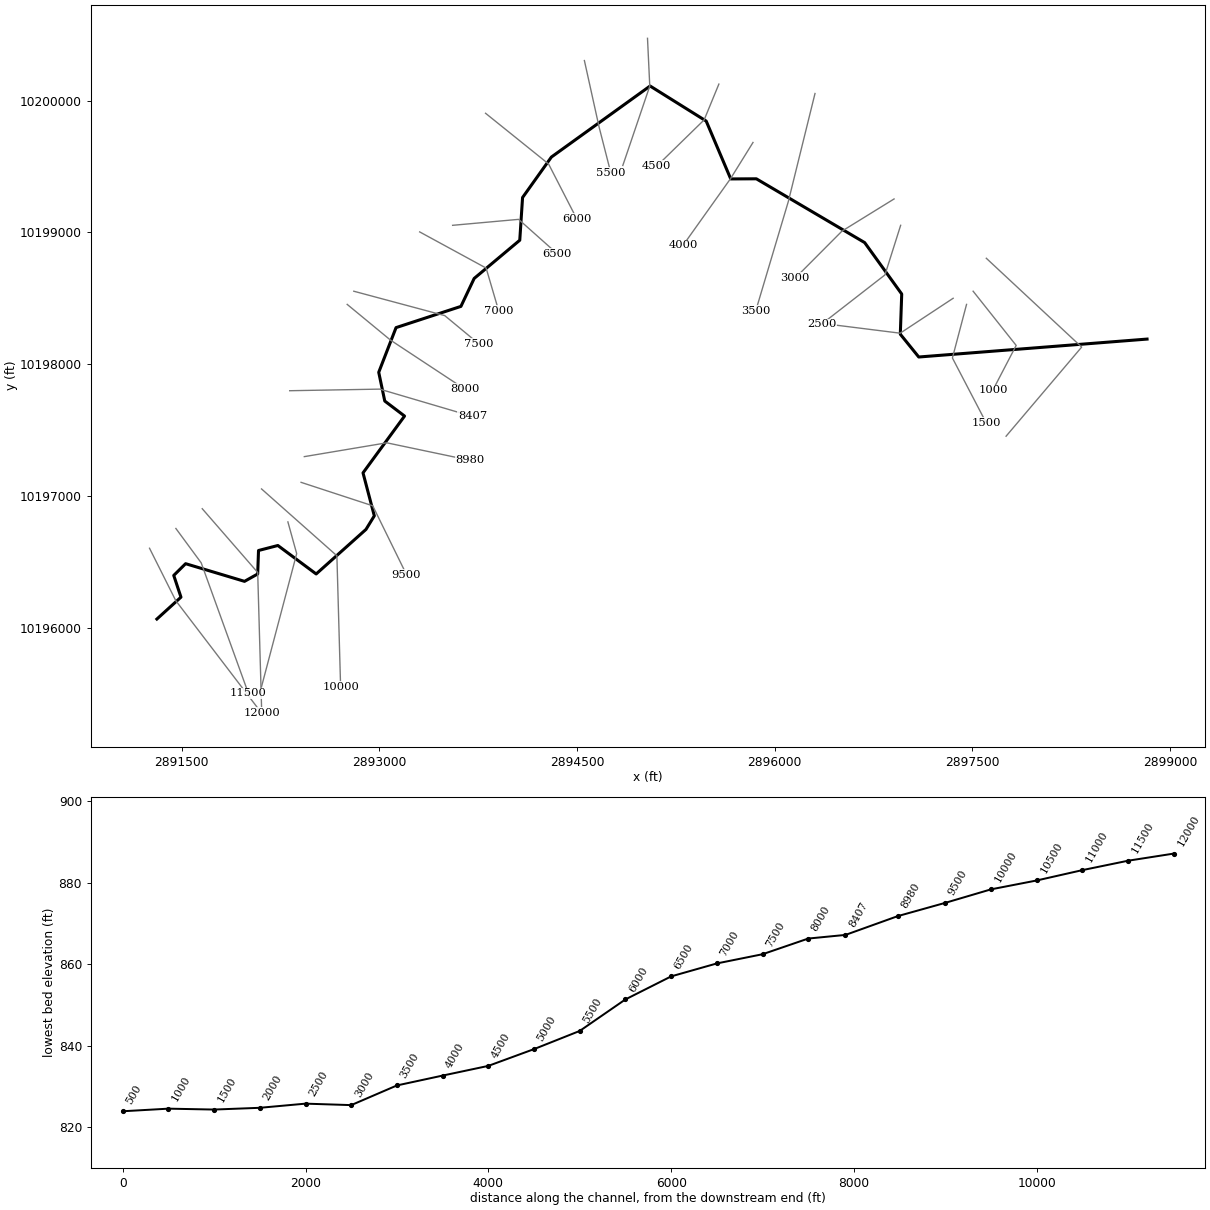
--- INKS 03.prj (project) ---

Proj Title=INKS 03 Base Level Engineering
Current Plan=p01
Default Exp/Contr=0.3,0.1
English Units
Geom File=g01
Flow File=f01
Plan File=p01
Y Axis Title=Elevation
X Axis Title(PF)=Main Channel Distance
X Axis Title(XS)=Station
BEGIN DESCRIPTION:
INKS 03
END DESCRIPTION:
DSS Export Rating Curves= 0
DSS Export Rating Curve Sorted= 0
DSS Export Volume Flow Curves= 0
DXF OffsetX= 0
DXF OffsetY= 0
DXF ScaleX= 1
DXF ScaleY= 10

--- INKS 03.p01 (plan) ---

Plan Title=Multiple Run
Short Identifier=Multiple
Geom File=g01
Flow File=f01
Subcritical Flow
K Sum by GR= 0
Std Step Tol= 0.01
Critical Tol= 0.01
Num of Std Step Trials= 20
Max Error Tol= 0.3
Flow Tol Ratio= 0.001
Split Flow NTrial= 30
Split Flow Tol= 0.02
Split Flow Ratio= 0.02
Log Output Level= 0
Friction Slope Method= 1
Unsteady Friction Slope Method= 2
Unsteady Bridges Friction Slope Method= 1
Parabolic Critical Depth
Global Vel Dist=  1 , 1 , 1
Global Log Level= 0
CheckData=True
Encroach Param= -1, 0, 0, 0
BEGIN DESCRIPTION:
Multiple Run
END DESCRIPTION:

--- INKS 03.f01 (steady flow) ---

Flow Title=Multiple
Number of Profiles=7
Profile Names=10-year,25-year,50-year,1pct_min,100-year,1pct_plu,500-year
River Rch & RM= INKS 03,Reach-1,12000
     453     736    1020     756    1368    2473    1891
River Rch & RM= INKS 03,Reach-1,6000
     769    1296    1784    1257    2430    4694    3340
Boundary for River Rch & Prof#=INKS 03,Reach-1,1
Up Type=0
Dn Type=3
Dn Slope=0.005
Boundary for River Rch & Prof#=INKS 03,Reach-1,2
Up Type=0
Dn Type=3
Dn Slope=0.005
Boundary for River Rch & Prof#=INKS 03,Reach-1,3
Up Type=0
Dn Type=3
Dn Slope=0.005
Boundary for River Rch & Prof#=INKS 03,Reach-1,4
Up Type=0
Dn Type=3
Dn Slope=0.005
Boundary for River Rch & Prof#=INKS 03,Reach-1,5
Up Type=0
Dn Type=3
Dn Slope=0.005
Boundary for River Rch & Prof#=INKS 03,Reach-1,6
Up Type=0
Dn Type=3
Dn Slope=0.005
Boundary for River Rch & Prof#=INKS 03,Reach-1,7
Up Type=0
Dn Type=3
Dn Slope=0.005

--- INKS 03.g01 (geometry) ---

Geom Title=Existing Conditions

River Reach=INKS 03,Reach-1
Reach XY= 30
      2891311.50     10196066.00      2891494.25     10196232.00
      2891439.50     10196397.00      2891529.50     10196486.00
      2891976.50     10196352.00      2892076.50     10196408.00
      2892082.75     10196586.00      2892229.50     10196624.00
      2892520.25     10196408.00      2892898.25     10196746.00
      2892961.50     10196849.00      2892875.75     10197175.00
      2893191.00     10197606.00      2893040.75     10197720.00
      2892995.00     10197938.00      2893126.50     10198277.00
      2893618.75     10198438.00      2893719.25     10198650.00
      2894065.25     10198940.00      2894086.50     10199264.00
      2894305.25     10199571.00      2895054.25     10200110.00
      2895480.00     10199844.00      2895666.25     10199405.00
      2895860.50     10199406.00      2896682.50     10198922.00
      2896963.75     10198532.00      2896953.00     10198227.00
      2897093.00     10198054.00      2898825.50     10198190.00

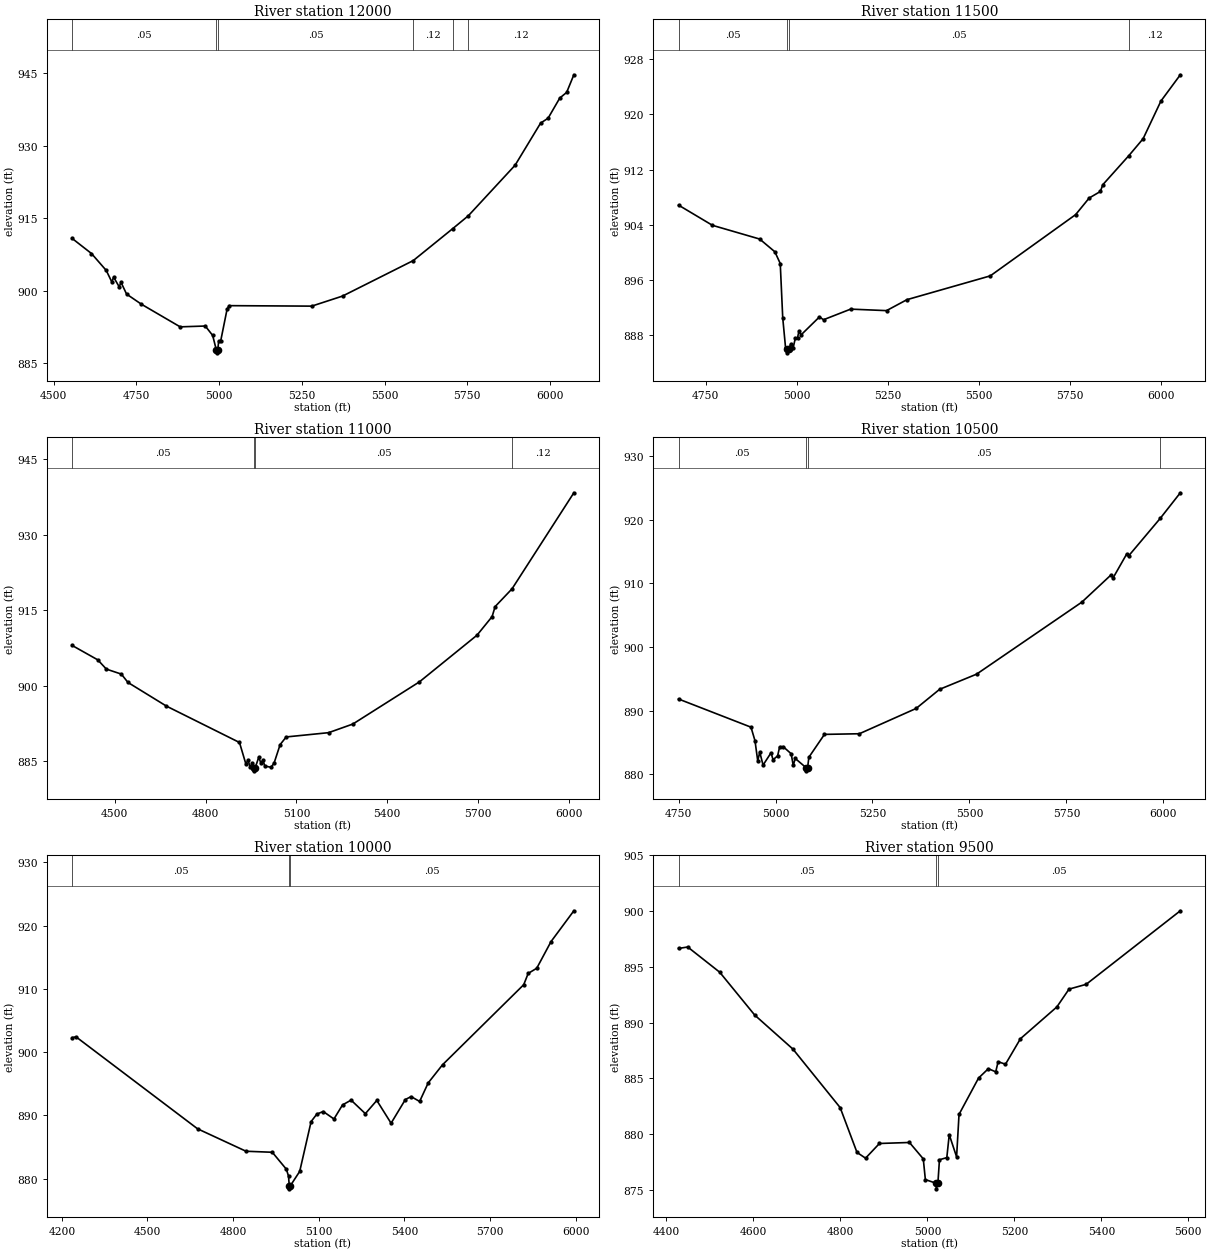
Type RM Length L Ch R = 1,12000,500,500,500
BEGIN DESCRIPTION:
INKS 03 24.0
END DESCRIPTION:
XS GIS Cut Line= 3
      2891255.68     10196603.11      2891454.89     10196205.64
      2892105.66     10195353.14
#Sta/Elev= 30
  4555.4  910.82  4614.1  907.69  4658.8  904.19  4675.5  901.82  4681.1  902.81
  4697.8  900.81  4703.4  901.73  4720.2  899.31  4764.9  897.22  4882.2  892.54
  4958.1  892.71  4980.5  890.77  4991.9  887.67  4992.2  887.17  4995.9  887.67
  4998.6  889.61  5004.7  889.61  5024.0  896.17  5030.3  896.92  5280.0  896.82
  5373.2  898.90  5586.9  906.23  5706.6  912.85  5753.3  915.48  5894.8  925.93
  5971.9  934.63  5994.6  935.65  6029.9  939.81  6050.7  940.98  6072.5  944.62
#Mann=6,-1,0
  4555.4    0.05       0  4991.9    0.03       0  4995.9    0.05       0
  5586.9    0.12       0  5706.6    0.05       0  5753.3    0.12       0
Bank Sta=4991.9,4995.9
Exp/Cntr=0.3,0.1

Type RM Length L Ch R = 1,11500,500,500,500
BEGIN DESCRIPTION:
INKS 03 23.0
END DESCRIPTION:
XS GIS Cut Line= 3
      2891455.67     10196753.13      2891647.82     10196492.26
      2892005.69     10195503.10
#Sta/Elev= 30
  4676.0  906.84  4769.0  903.91  4898.5  901.92  4940.2  900.07  4954.9  898.37
  4961.7  890.50  4969.5  886.13  4973.7  885.92  4974.0  885.42  4977.7  885.92
  4984.1  886.72  4990.3  886.13  4996.4  887.60  5002.2  887.60  5006.4  888.61
  5011.7  888.01  5062.4  890.63  5073.5  890.22  5148.0  891.76  5246.3  891.54
  5302.3  893.13  5530.8  896.58  5764.8  905.46  5802.0  907.87  5832.7  908.82
  5839.2  909.79  5911.0  914.03  5949.9  916.47  5998.7  921.93  6051.9  925.74
#Mann=4,-1,0
  4676.0    0.05       0  4973.7    0.03       0  4977.7    0.05       0
  5911.0    0.12       0
Bank Sta=4973.7,4977.7
Exp/Cntr=0.3,0.1

Type RM Length L Ch R = 1,11000,500,500,500
BEGIN DESCRIPTION:
INKS 03 22.0
END DESCRIPTION:
XS GIS Cut Line= 3
      2891655.70     10196903.09      2892076.50     10196419.42
      2892105.68     10195403.14
#Sta/Elev= 30
  4358.9  908.02  4443.8  905.15  4472.3  903.31  4521.7  902.32  4543.6  900.66
  4670.8  895.96  4912.0  888.74  4932.8  884.53  4940.4  885.21  4947.1  883.86
  4954.7  884.64  4959.3  883.61  4959.6  883.11  4963.3  883.61  4975.6  885.80
  4982.2  884.74  4989.8  885.19  4995.6  884.06  5016.3  883.82  5026.3  884.65
  5046.3  888.32  5066.3  889.84  5206.4  890.69  5286.4  892.40  5506.5  900.78
  5696.6  910.04  5746.6  913.74  5756.6  915.73  5812.5  919.26  6016.7  938.33
#Mann=4,-1,0
  4358.9    0.05       0  4959.3    0.05       0  4963.3    0.05       0
  5812.5    0.12       0
Bank Sta=4959.3,4963.3
Exp/Cntr=0.3,0.1

Type RM Length L Ch R = 1,10500,500,500,500
BEGIN DESCRIPTION:
INKS 03 21.0
END DESCRIPTION:
XS GIS Cut Line= 3
      2892305.69     10196803.10      2892372.41     10196562.17
      2892105.69     10195553.12
#Sta/Elev= 30
  4750.0  891.84  4936.8  887.42  4947.1  885.30  4954.2  882.13  4959.4  883.51
  4967.9  881.47  4988.5  883.40  4993.7  882.31  5005.5  882.92  5010.6  884.33
  5019.7  884.37  5040.4  883.25  5045.7  881.42  5050.9  882.51  5078.8  881.07
  5079.1  880.57  5082.8  881.07  5086.0  882.70  5126.2  886.29  5216.2  886.39
  5362.6  890.36  5423.1  893.36  5518.4  895.74  5789.8  907.04  5865.2  911.32
  5870.3  910.84  5905.4  914.59  5910.6  914.31  5991.7  920.17  6043.7  924.20
#Mann=4,-1,0
  4750.0    0.05       0  5078.8    0.05       0  5082.8    0.05       0
  5991.7    0.12       0
Bank Sta=5078.8,5082.8
Exp/Cntr=0.3,0.1

Type RM Length L Ch R = 1,10000,500,500,500
BEGIN DESCRIPTION:
INKS 03 20.0
END DESCRIPTION:
XS GIS Cut Line= 3
      2892105.66     10197053.13      2892677.48     10196546.15
      2892705.68     10195553.15
#Sta/Elev= 30
  4235.8  902.28  4249.6  902.41  4675.3  887.88  4845.1  884.33  4937.1  884.17
  4986.4  881.49  4994.0  880.39  4996.5  878.89  4996.8  878.39  5000.5  878.89
  5033.1  881.14  5073.1  889.02  5093.1  890.20  5115.5  890.61  5153.1  889.43
  5183.1  891.65  5213.1  892.41  5263.1  890.27  5303.2  892.36  5353.2  888.76
  5403.2  892.50  5423.2  892.97  5453.2  892.20  5483.2  895.13  5533.3  897.99
  5817.8  910.65  5833.4  912.43  5863.4  913.25  5913.4  917.46  5993.4  922.33
#Mann=3,-1,0
  4235.8    0.05       0  4996.5    0.05       0  5000.5    0.05       0
Bank Sta=4996.5,5000.5
Exp/Cntr=0.3,0.1

Type RM Length L Ch R = 1,9500,520,520,520
BEGIN DESCRIPTION:
INKS 03 19.0
END DESCRIPTION:
XS GIS Cut Line= 3
      2892405.73     10197103.10      2892949.55     10196925.13
      2893205.70     10196403.09
#Sta/Elev= 30
  4427.8  896.65  4448.9  896.78  4522.4  894.52  4603.0  890.67  4690.8  887.62
  4799.4  882.37  4838.1  878.35  4857.8  877.83  4889.7  879.15  4958.7  879.24
  4990.5  877.77  4995.3  875.91  5020.1  875.58  5020.4  875.08  5024.1  875.58
  5027.7  877.69  5044.6  877.88  5050.2  879.94  5067.1  877.95  5072.7  881.76
  5117.6  885.02  5140.1  885.86  5157.1  885.58  5162.6  886.49  5179.5  886.26
  5213.9  888.55  5297.6  891.40  5325.6  893.00  5365.0  893.43  5581.5  900.03
#Mann=3,-1,0
  4427.8    0.05       0  5020.1    0.05       0  5024.1    0.05       0
Bank Sta=5020.1,5024.1
Exp/Cntr=0.3,0.1

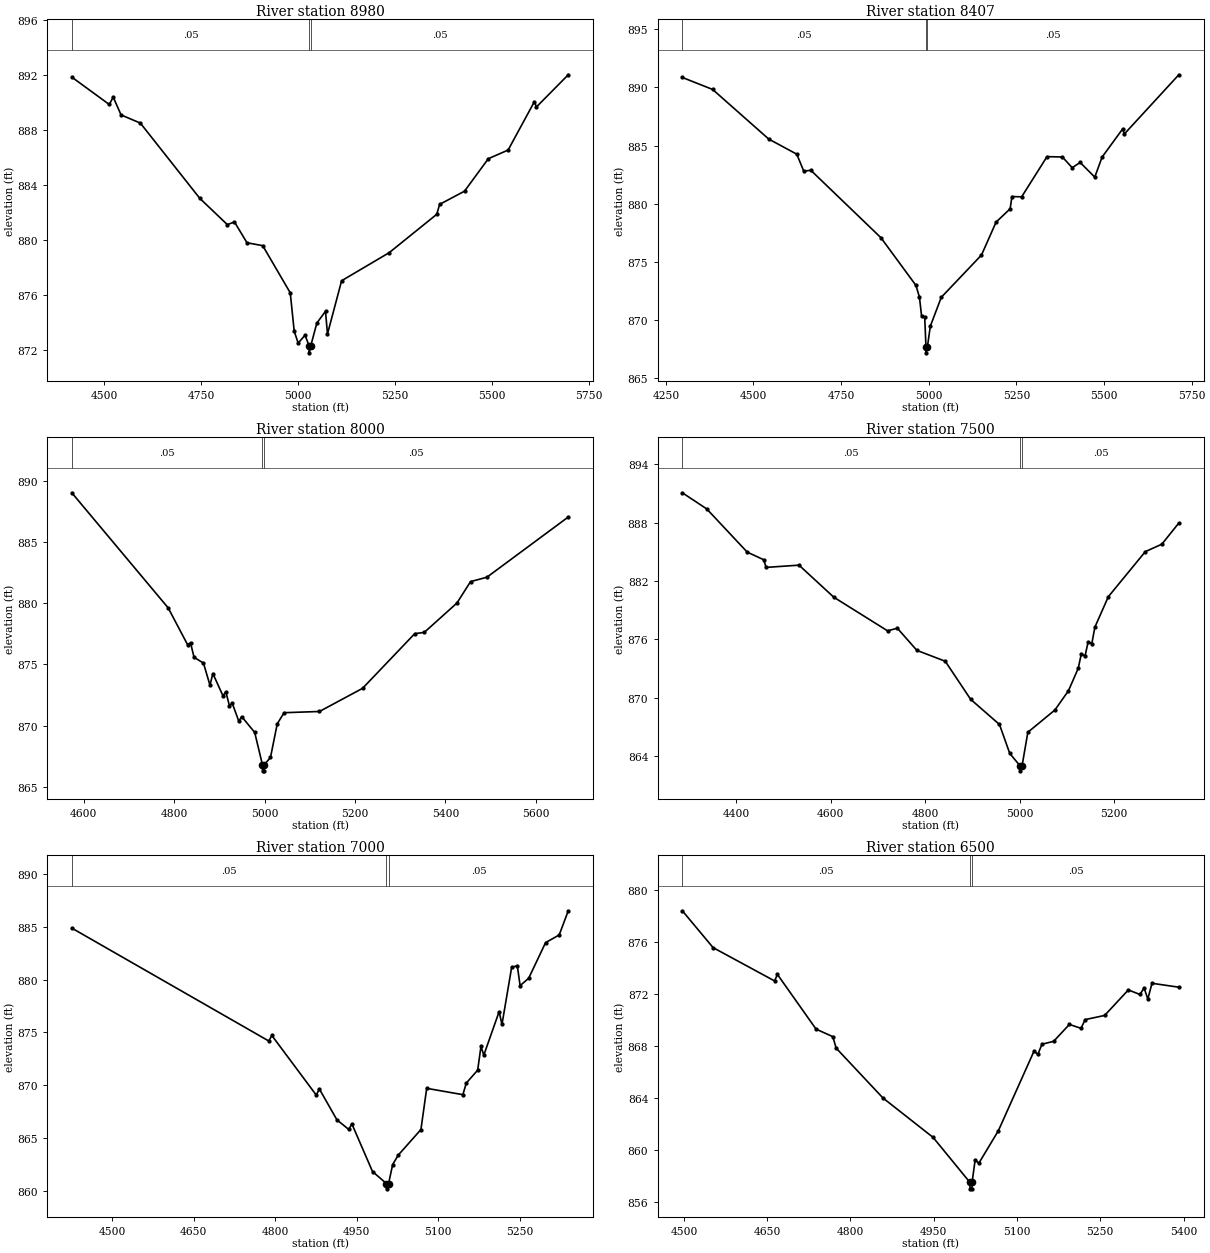
Type RM Length L Ch R = 1,8980,573,573,573
BEGIN DESCRIPTION:
INKS 03 18.0
END DESCRIPTION:
XS GIS Cut Line= 3
      2892430.45     10197298.22      2893055.68     10197403.11
      2893687.33     10197270.44
#Sta/Elev= 30
  4416.5  891.86  4513.1  889.87  4523.2  890.41  4543.5  889.11  4593.1  888.52
  4746.3  883.05  4817.3  881.14  4835.7  881.33  4868.0  879.82  4908.5  879.61
  4979.5  876.18  4989.6  873.40  4999.8  872.53  5017.6  873.10  5028.2  872.32
  5028.4  871.82  5032.2  872.32  5047.9  873.98  5070.3  874.84  5075.4  873.19
  5111.8  877.06  5234.4  879.10  5357.0  881.89  5364.4  882.61  5428.5  883.57
  5489.9  885.93  5540.9  886.56  5608.7  890.08  5613.8  889.69  5695.9  892.03
#Mann=3,-1,0
  4416.5    0.05       0  5028.2    0.05       0  5032.2    0.05       0
Bank Sta=5028.2,5032.2
Exp/Cntr=0.3,0.1

Type RM Length L Ch R = 1,8407,407,407,407
BEGIN DESCRIPTION:
INKS 03 17.0
END DESCRIPTION:
XS GIS Cut Line= 3
      2892319.26     10197798.22      2893002.33     10197810.37
      2893705.66     10197603.12
#Sta/Elev= 30
  4297.0  890.85  4383.4  889.82  4543.5  885.56  4623.5  884.26  4643.5  882.80
  4663.5  882.88  4863.5  877.09  4963.5  872.99  4973.5  871.98  4979.4  870.39
  4988.5  870.25  4992.1  867.70  4992.3  867.20  4996.1  867.70  5004.5  869.49
  5035.8  871.97  5150.5  875.60  5192.2  878.43  5232.2  879.57  5237.4  880.62
  5265.1  880.60  5337.4  884.05  5381.2  884.02  5409.3  883.10  5432.0  883.55
  5473.7  882.29  5494.5  884.01  5553.0  886.42  5558.2  886.00  5713.4  891.08
#Mann=3,-1,0
  4297.0    0.05       0  4992.1    0.05       0  4996.1    0.05       0
Bank Sta=4992.1,4996.1
Exp/Cntr=0.3,0.1

Type RM Length L Ch R = 1,8000,500,500,500
BEGIN DESCRIPTION:
INKS 03 16.0
END DESCRIPTION:
XS GIS Cut Line= 3
      2892755.66     10198453.13      2893084.63     10198182.00
      2893645.68     10197812.12
#Sta/Elev= 30
  4573.7  889.03  4786.8  879.63  4829.8  876.62  4836.3  876.78  4844.1  875.59
  4865.0  875.11  4879.3  873.31  4885.8  874.26  4908.0  872.45  4914.5  872.76
  4922.3  871.64  4928.8  871.82  4943.1  870.37  4949.6  870.74  4978.3  869.45
  4995.4  866.81  4995.7  866.31  4999.2  866.31  4999.4  866.81  5013.2  867.40
  5028.2  870.15  5043.3  871.06  5121.6  871.16  5216.9  873.05  5332.4  877.52
  5353.4  877.62  5425.7  880.02  5455.8  881.77  5492.0  882.13  5672.0  887.05
#Mann=3,-1,0
  4573.7    0.05       0  4995.4    0.05       0  4999.4    0.05       0
Bank Sta=4995.4,4999.4
Exp/Cntr=0.3,0.1

Type RM Length L Ch R = 1,7500,500,500,500
BEGIN DESCRIPTION:
INKS 03 15.0
END DESCRIPTION:
XS GIS Cut Line= 3
      2892805.72     10198553.10      2893495.97     10198368.14
      2893755.70     10198153.10
#Sta/Elev= 30
  4285.4  891.08  4337.1  889.42  4422.9  884.97  4457.7  884.19  4462.9  883.40
  4532.6  883.63  4606.3  880.33  4720.2  876.87  4740.9  877.14  4782.3  874.86
  4842.4  873.74  4896.2  869.82  4957.3  867.23  4979.0  864.26  5001.1  862.96
  5001.3  862.46  5005.1  862.96  5017.4  866.43  5074.7  868.72  5103.4  870.70
  5124.2  873.02  5130.7  874.51  5138.6  874.28  5145.1  875.74  5152.9  875.54
  5159.4  877.25  5188.0  880.39  5266.2  885.02  5301.3  885.79  5337.2  887.96
#Mann=3,-1,0
  4285.4    0.05       0  5001.1    0.05       0  5005.1    0.05       0
Bank Sta=5001.1,5005.1
Exp/Cntr=0.3,0.1

Type RM Length L Ch R = 1,7000,500,500,500
BEGIN DESCRIPTION:
INKS 03 14.0
END DESCRIPTION:
XS GIS Cut Line= 3
      2893305.67     10199003.12      2893810.03     10198728.67
      2893905.68     10198403.13
#Sta/Elev= 30
  4425.8  884.87  4788.2  874.19  4793.9  874.71  4875.6  869.07  4881.3  869.65
  4913.6  866.73  4935.4  865.82  4941.1  866.35  4979.1  861.84  5004.7  860.70
  5004.9  860.20  5008.7  860.70  5016.2  862.50  5026.6  863.40  5068.2  865.81
  5078.8  869.71  5145.4  869.11  5151.7  870.21  5172.6  871.43  5178.7  873.68
  5183.9  872.85  5212.1  876.97  5217.3  875.75  5235.1  881.15  5245.5  881.32
  5250.7  879.43  5266.4  880.12  5297.6  883.50  5322.6  884.22  5339.3  886.51
#Mann=3,-1,0
  4425.8    0.05       0  5004.7    0.05       0  5008.7    0.05       0
Bank Sta=5004.7,5008.7
Exp/Cntr=0.3,0.1

Type RM Length L Ch R = 1,6500,500,500,500
BEGIN DESCRIPTION:
INKS 03 13.0
END DESCRIPTION:
XS GIS Cut Line= 3
      2893555.71     10199053.11      2894056.58     10199098.32
      2894348.95     10198837.95
#Sta/Elev= 30
  4497.1  878.38  4552.5  875.55  4663.3  872.99  4668.4  873.49  4738.0  869.29
  4768.2  868.71  4774.2  867.83  4858.5  864.00  4948.9  860.97  5015.1  857.52
  5015.4  857.02  5018.9  857.02  5019.1  857.52  5024.6  859.24  5031.3  858.99
  5066.5  861.49  5130.8  867.61  5137.5  867.34  5145.0  868.13  5166.0  868.35
  5194.4  869.65  5215.3  869.35  5222.8  870.02  5257.9  870.34  5300.6  872.30
  5321.5  871.95  5329.0  872.45  5335.7  871.60  5343.2  872.81  5391.5  872.51
#Mann=3,-1,0
  4497.1    0.05       0  5015.1    0.05       0  5019.1    0.05       0
Bank Sta=5015.1,5019.1
Exp/Cntr=0.3,0.1

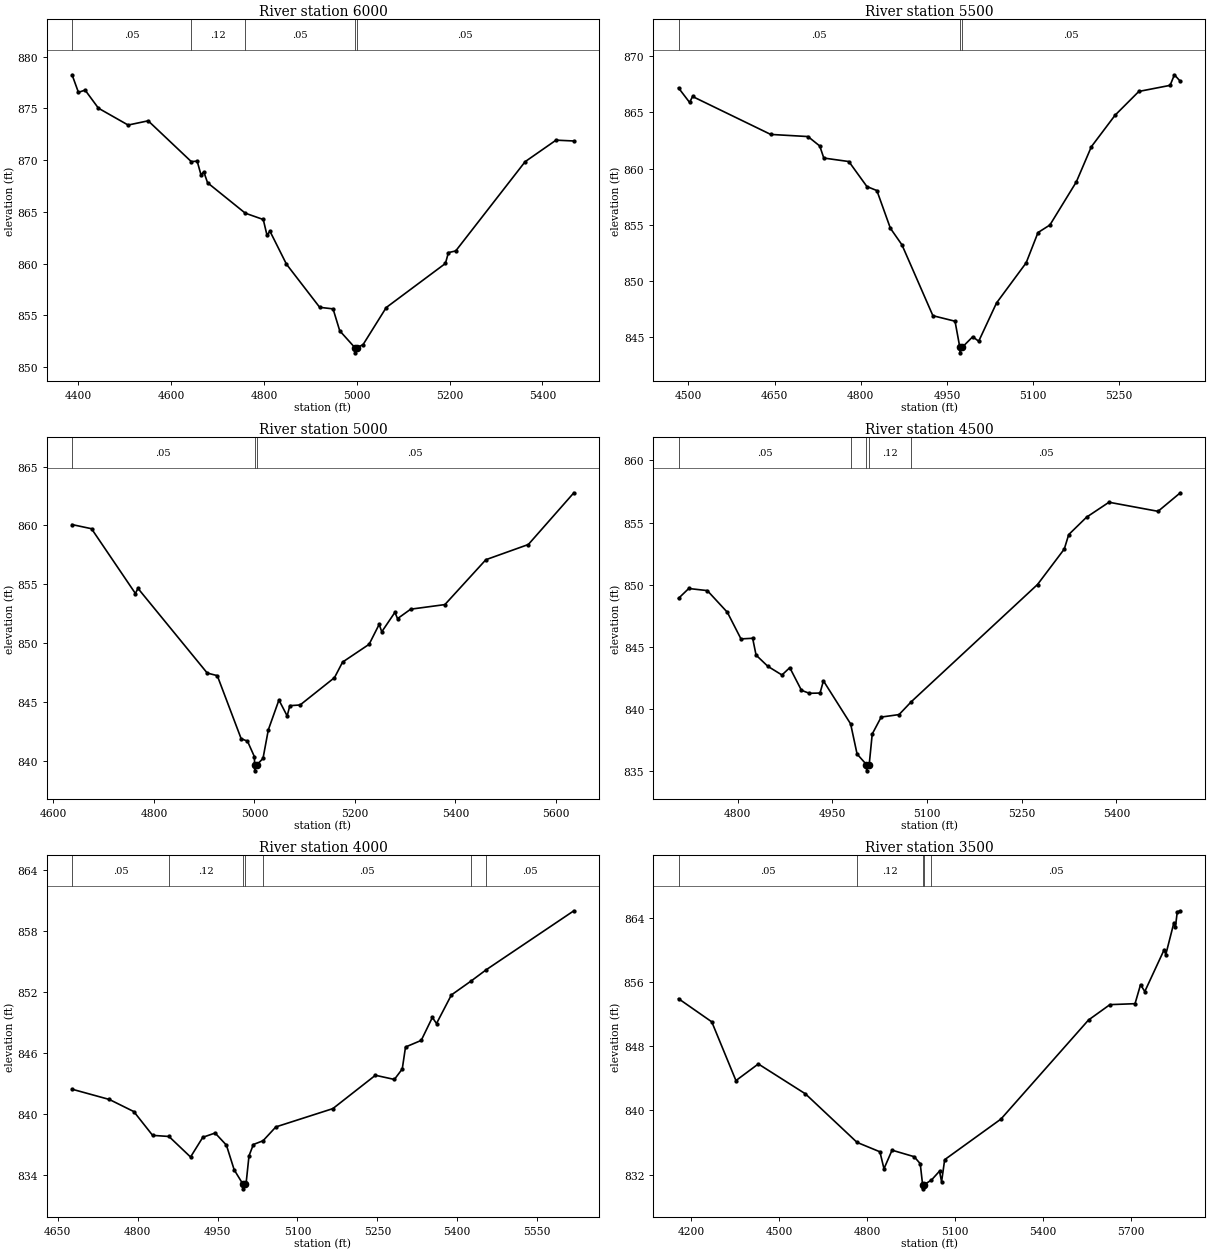
Type RM Length L Ch R = 1,6000,500,500,500
BEGIN DESCRIPTION:
INKS 03 12.0
END DESCRIPTION:
XS GIS Cut Line= 3
      2893805.65     10199903.14      2894283.84     10199518.65
      2894497.60     10199102.65
#Sta/Elev= 30
  4386.4  878.25  4400.1  876.55  4414.5  876.77  4443.2  875.02  4507.2  873.39
  4550.4  873.80  4643.2  869.86  4656.0  869.90  4664.0  868.61  4670.4  868.85
  4678.4  867.81  4759.7  864.87  4798.4  864.26  4806.4  862.75  4812.8  863.13
  4848.4  859.94  4920.0  855.77  4948.8  855.62  4963.2  853.50  4995.9  851.87
  4996.2  851.37  5000.0  851.87  5013.4  852.16  5063.4  855.75  5190.9  860.01
  5197.4  861.06  5213.1  861.22  5362.7  869.85  5429.3  871.93  5467.7  871.85
#Mann=5,-1,0
  4386.4    0.05       0  4643.2    0.12       0  4759.7    0.05       0
  4995.9    0.05       0  5000.0    0.05       0
Bank Sta=4995.9,5000
Exp/Cntr=0.3,0.1

Type RM Length L Ch R = 1,5500,500,500,500
BEGIN DESCRIPTION:
INKS 03 11.0
END DESCRIPTION:
XS GIS Cut Line= 3
      2894555.68     10200303.13      2894667.37     10199798.24
      2894755.67     10199453.16
#Sta/Elev= 30
  4482.9  867.17  4502.2  865.88  4507.3  866.41  4643.3  863.04  4708.2  862.85
  4728.7  862.01  4735.7  860.94  4779.3  860.63  4810.7  858.41  4828.1  858.05
  4851.6  854.70  4871.7  853.23  4925.6  846.93  4964.1  846.44  4972.4  844.13
  4972.7  843.63  4976.7  844.13  4994.9  845.06  5005.3  844.66  5036.3  848.06
  5087.9  851.63  5108.5  854.32  5129.2  854.99  5175.2  858.82  5201.4  861.95
  5242.7  864.75  5284.0  866.86  5338.4  867.40  5345.9  868.34  5356.2  867.76
#Mann=3,-1,0
  4482.9    0.05       0  4972.4    0.05       0  4976.7    0.05       0
Bank Sta=4972.4,4976.7
Exp/Cntr=0.3,0.1

Type RM Length L Ch R = 1,5000,500,500,500
BEGIN DESCRIPTION:
INKS 03 10.0
END DESCRIPTION:
XS GIS Cut Line= 3
      2895034.59     10200471.79      2895051.83     10200109.20
      2894847.34     10199507.29
#Sta/Elev= 30
  4637.0  860.07  4675.7  859.72  4763.1  854.22  4768.1  854.66  4906.0  847.47
  4926.0  847.25  4973.5  841.90  4986.1  841.69  5000.0  840.36  5000.2  839.67
  5000.5  839.17  5004.5  839.67  5017.0  840.22  5027.6  842.65  5048.7  845.18
  5065.1  843.83  5070.4  844.70  5090.9  844.76  5159.3  847.08  5175.4  848.40
  5228.2  849.91  5248.2  851.60  5253.4  850.97  5279.5  852.62  5284.8  852.09
  5310.9  852.89  5379.0  853.28  5460.6  857.09  5545.1  858.38  5635.7  862.77
#Mann=3,-1,0
  4637.0    0.05       0  5000.2    0.05       0  5004.5    0.05       0
Bank Sta=5000.2,5004.5
Exp/Cntr=0.3,0.1

Type RM Length L Ch R = 1,4500,500,500,500
BEGIN DESCRIPTION:
INKS 03 9.0
END DESCRIPTION:
XS GIS Cut Line= 3
      2895576.25     10200124.60      2895464.51     10199853.09
      2895105.71     10199503.14
#Sta/Elev= 30
  4706.4  848.91  4722.6  849.70  4752.0  849.53  4783.7  847.79  4805.3  845.65
  4823.8  845.70  4829.2  844.35  4847.8  843.45  4870.2  842.75  4882.6  843.34
  4901.1  841.52  4913.5  841.28  4930.5  841.30  4935.9  842.28  4979.0  838.82
  4989.2  836.40  5004.1  835.55  5004.3  835.05  5008.4  835.55  5013.2  838.01
  5027.4  839.37  5055.7  839.57  5075.2  840.61  5275.0  850.02  5317.4  852.87
  5324.4  854.03  5352.7  855.43  5388.2  856.63  5465.9  855.90  5501.2  857.39
#Mann=5,-1,0
  4706.4    0.05       0  4979.0    0.12       0  5004.1    0.07       0
  5008.4    0.12       0  5075.2    0.05       0
Bank Sta=5004.1,5008.4
Exp/Cntr=0.3,0.1

Type RM Length L Ch R = 1,4000,500,500,500
BEGIN DESCRIPTION:
INKS 03 8.0
END DESCRIPTION:
XS GIS Cut Line= 3
      2895835.13     10199681.60      2895664.70     10199407.11
      2895305.68     10198903.11
#Sta/Elev= 30
  4676.9  842.47  4746.9  841.46  4792.8  840.27  4828.1  837.93  4858.8  837.82
  4899.3  835.80  4922.3  837.74  4945.4  838.16  4966.6  836.97  4981.2  834.54
  4997.2  833.17  4997.5  832.67  5001.7  833.17  5003.5  833.17  5009.0  835.91
  5017.2  837.03  5035.4  837.40  5059.4  838.76  5166.4  840.56  5246.3  843.84
  5281.9  843.43  5296.7  844.46  5302.8  846.62  5332.3  847.27  5353.2  849.53
  5361.0  848.93  5388.9  851.74  5426.4  853.13  5454.6  854.23  5618.8  860.02
#Mann=7,-1,0
  4676.9    0.05       0  4858.8    0.12       0  4997.2    0.07       0
  5001.7    0.12       0  5035.4    0.05       0  5426.4    0.12       0
  5454.6    0.05       0
Bank Sta=4997.2,5001.7
Exp/Cntr=0.3,0.1

Type RM Length L Ch R = 1,3500,500,500,500
BEGIN DESCRIPTION:
INKS 03 7.0
END DESCRIPTION:
XS GIS Cut Line= 3
      2896305.68     10200053.09      2896103.51     10199234.69
      2895855.69     10198403.13
#Sta/Elev= 30
  4157.0  853.91  4270.3  851.03  4352.7  843.72  4429.0  845.79  4589.6  842.07
  4765.6  836.03  4843.5  834.86  4857.4  832.75  4884.9  835.06  4960.4  834.25
  4981.0  833.38  4989.1  830.75  4989.4  830.25  4993.6  830.75  5019.4  831.35
  5046.7  832.45  5053.8  831.13  5064.3  833.88  5256.1  838.93  5554.7  851.26
  5627.7  853.17  5713.3  853.29  5732.1  855.66  5746.5  854.80  5812.8  860.02
  5818.0  859.38  5845.9  863.38  5851.1  862.88  5857.3  864.72  5867.7  864.85
#Mann=5,-1,0
  4157.0    0.05       0  4765.6    0.12       0  4989.1    0.07       0
  4993.6    0.12       0  5019.4    0.05       0
Bank Sta=4989.1,4993.6
Exp/Cntr=0.3,0.1

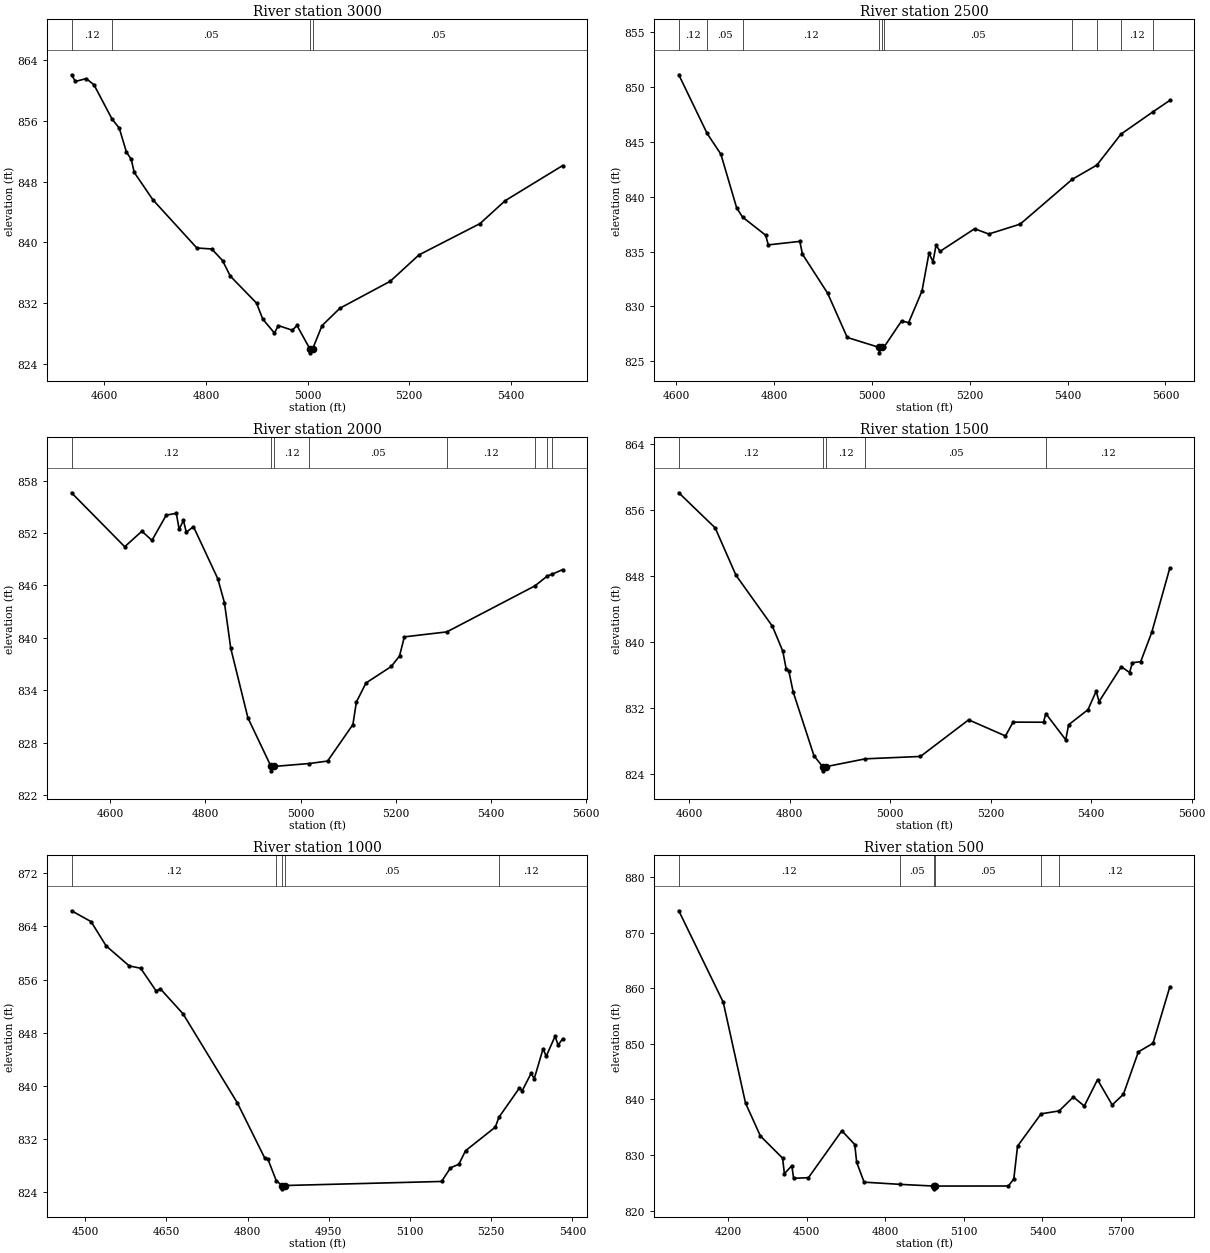
Type RM Length L Ch R = 1,3000,500,500,500
BEGIN DESCRIPTION:
INKS 03 6.0
END DESCRIPTION:
XS GIS Cut Line= 3
      2896905.66     10199253.09      2896510.17     10199008.91
      2896155.72     10198653.14
#Sta/Elev= 30
  4535.2  862.10  4542.9  861.22  4564.1  861.60  4579.5  860.77  4614.9  856.27
  4629.2  855.06  4643.3  851.90  4652.7  850.96  4658.7  849.22  4695.4  845.61
  4782.0  839.25  4811.3  839.12  4832.5  837.60  4847.9  835.54  4899.5  831.98
  4911.7  829.88  4934.8  828.03  4942.5  829.02  4970.0  828.40  4979.2  829.03
  5004.7  825.92  5005.1  825.42  5009.9  825.92  5028.5  829.01  5063.8  831.31
  5162.8  834.86  5219.4  838.34  5339.6  842.47  5389.1  845.49  5502.2  850.12
#Mann=4,-1,0
  4535.2    0.12       0  4614.9    0.05       0  5004.7    0.05       0
  5009.9    0.05       0
Bank Sta=5004.7,5009.9
Exp/Cntr=0.3,0.1

Type RM Length L Ch R = 1,2500,500,500,500
BEGIN DESCRIPTION:
INKS 03 5.0
END DESCRIPTION:
XS GIS Cut Line= 3
      2896955.69     10199053.14      2896836.44     10198676.78
      2896355.68     10198303.11
#Sta/Elev= 30
  4605.2  851.10  4663.1  845.76  4691.2  843.87  4723.5  838.98  4735.5  838.14
  4782.8  836.49  4788.1  835.61  4852.6  835.93  4857.9  834.77  4909.4  831.21
  4949.5  827.18  5014.4  826.28  5014.8  825.78  5019.6  826.28  5025.0  826.33
  5060.5  828.68  5075.0  828.53  5102.3  831.41  5116.6  834.86  5124.7  834.07
  5131.1  835.59  5139.2  835.02  5209.8  837.08  5238.8  836.60  5303.0  837.50
  5409.4  841.58  5459.8  842.88  5509.1  845.70  5574.8  847.74  5608.9  848.77
#Mann=10,-1,0
  4605.2    0.12       0  4663.1    0.05       0  4735.5    0.12       0
  5014.4    0.07       0  5019.6    0.12       0  5025.0    0.05       0
  5409.4    0.12       0  5459.8    0.05       0  5509.1    0.12       0
  5574.8    0.05       0
Bank Sta=5014.4,5019.6
Exp/Cntr=0.3,0.1

Type RM Length L Ch R = 1,2000,500,500,500
BEGIN DESCRIPTION:
INKS 03 4.0
END DESCRIPTION:
XS GIS Cut Line= 3
      2897354.03     10198499.61      2896952.18     10198234.71
      2896405.65     10198303.12
#Sta/Elev= 30
  4518.7  856.60  4630.5  850.42  4666.6  852.20  4687.7  851.15  4717.8  854.04
  4738.9  854.25  4744.9  852.42  4753.9  853.44  4759.9  852.08  4775.0  852.72
  4826.2  846.75  4840.1  844.01  4853.3  838.81  4889.4  830.83  4938.0  825.26
  4938.4  824.76  4943.3  825.26  5018.7  825.60  5056.9  825.88  5110.1  830.06
  5117.4  832.64  5137.6  834.82  5190.7  836.71  5208.1  837.91  5218.2  840.10
  5307.5  840.67  5492.7  845.94  5519.0  847.08  5529.5  847.29  5550.8  847.80
#Mann=8,-1,0
  4518.7    0.12       0  4938.0    0.07       0  4943.3    0.12       0
  5018.7    0.05       0  5307.5    0.12       0  5492.7    0.05       0
  5519.0    0.12       0  5529.5    0.05       0
Bank Sta=4938,4943.3
Exp/Cntr=0.3,0.1

Type RM Length L Ch R = 1,1500,500,500,500
BEGIN DESCRIPTION:
INKS 03 3.0
END DESCRIPTION:
XS GIS Cut Line= 3
      2897455.69     10198453.12      2897348.46     10198046.73
      2897605.67     10197553.13
#Sta/Elev= 30
  4579.7  858.13  4652.1  853.86  4693.5  848.10  4765.9  841.91  4786.6  838.88
  4793.5  836.66  4798.7  836.44  4807.2  833.93  4848.6  826.17  4865.9  824.83
  4866.4  824.33  4871.9  824.83  4950.8  825.79  5060.5  826.08  5156.3  830.53
  5229.6  828.57  5244.7  830.25  5305.3  830.24  5309.8  831.29  5349.5  828.10
  5355.2  829.93  5393.7  831.76  5410.0  834.01  5415.8  832.75  5460.0  836.99
  5476.5  836.28  5482.1  837.47  5498.6  837.60  5520.7  841.18  5556.6  848.99
#Mann=5,-1,0
  4579.7    0.12       0  4865.9    0.03       0  4871.9    0.12       0
  4950.8    0.05       0  5309.8    0.12       0
Bank Sta=4865.9,4871.9
Exp/Cntr=0.3,0.1

Type RM Length L Ch R = 1,1000,500,500,500
BEGIN DESCRIPTION:
INKS 03 2.0
END DESCRIPTION:
XS GIS Cut Line= 3
      2897505.67     10198553.13      2897832.27     10198141.84
      2897655.68     10197803.11
#Sta/Elev= 30
  4474.8  866.36  4510.9  864.73  4538.7  861.08  4581.4  858.07  4602.5  857.72
  4631.0  854.32  4639.1  854.61  4680.7  850.88  4781.3  837.45  4831.3  829.25
  4837.7  828.99  4852.9  825.80  4863.5  825.05  4864.0  824.55  4869.5  825.05
  5158.5  825.66  5174.9  827.71  5190.3  828.25  5202.7  830.28  5257.7  833.83
  5264.3  835.30  5301.8  839.66  5307.5  839.32  5323.9  841.92  5329.6  841.10
  5346.0  845.62  5351.7  844.48  5368.1  847.49  5373.8  846.16  5382.0  847.11
#Mann=5,-1,0
  4474.8    0.12       0  4852.9    0.05       0  4863.5    0.03       0
  4869.5    0.05       0  5264.3    0.12       0
Bank Sta=4863.5,4869.5
Exp/Cntr=0.3,0.1

Type RM Length L Ch R = 1,500,0,0,0
BEGIN DESCRIPTION:
INKS 03 1.0
END DESCRIPTION:
XS GIS Cut Line= 3
      2897605.69     10198803.10      2898329.20     10198129.26
      2897755.70     10197453.13
#Sta/Elev= 30
  4011.3  873.91  4181.1  857.46  4266.1  839.34  4322.8  833.42  4407.6  829.43
  4414.6  826.63  4442.9  828.07  4449.8  825.81  4506.4  825.91  4634.0  834.35
  4683.3  831.88  4690.6  828.69  4719.0  825.11  4855.0  824.72  4984.6  824.41
  4985.1  823.91  4990.7  824.41  5269.9  824.42  5290.7  825.69  5305.0  831.59
  5394.9  837.40  5463.8  837.92  5518.1  840.43  5559.8  838.80  5610.4  843.54
  5666.4  839.00  5709.2  840.91  5766.4  848.54  5822.3  850.09  5886.6  860.25
#Mann=6,-1,0
  4011.3    0.12       0  4855.0    0.05       0  4984.6    0.03       0
  4990.7    0.05       0  5394.9    0.05       0  5463.8    0.12       0
Bank Sta=4984.6,4990.7
Exp/Cntr=0.3,0.1

Chan Stop Cuts=-1