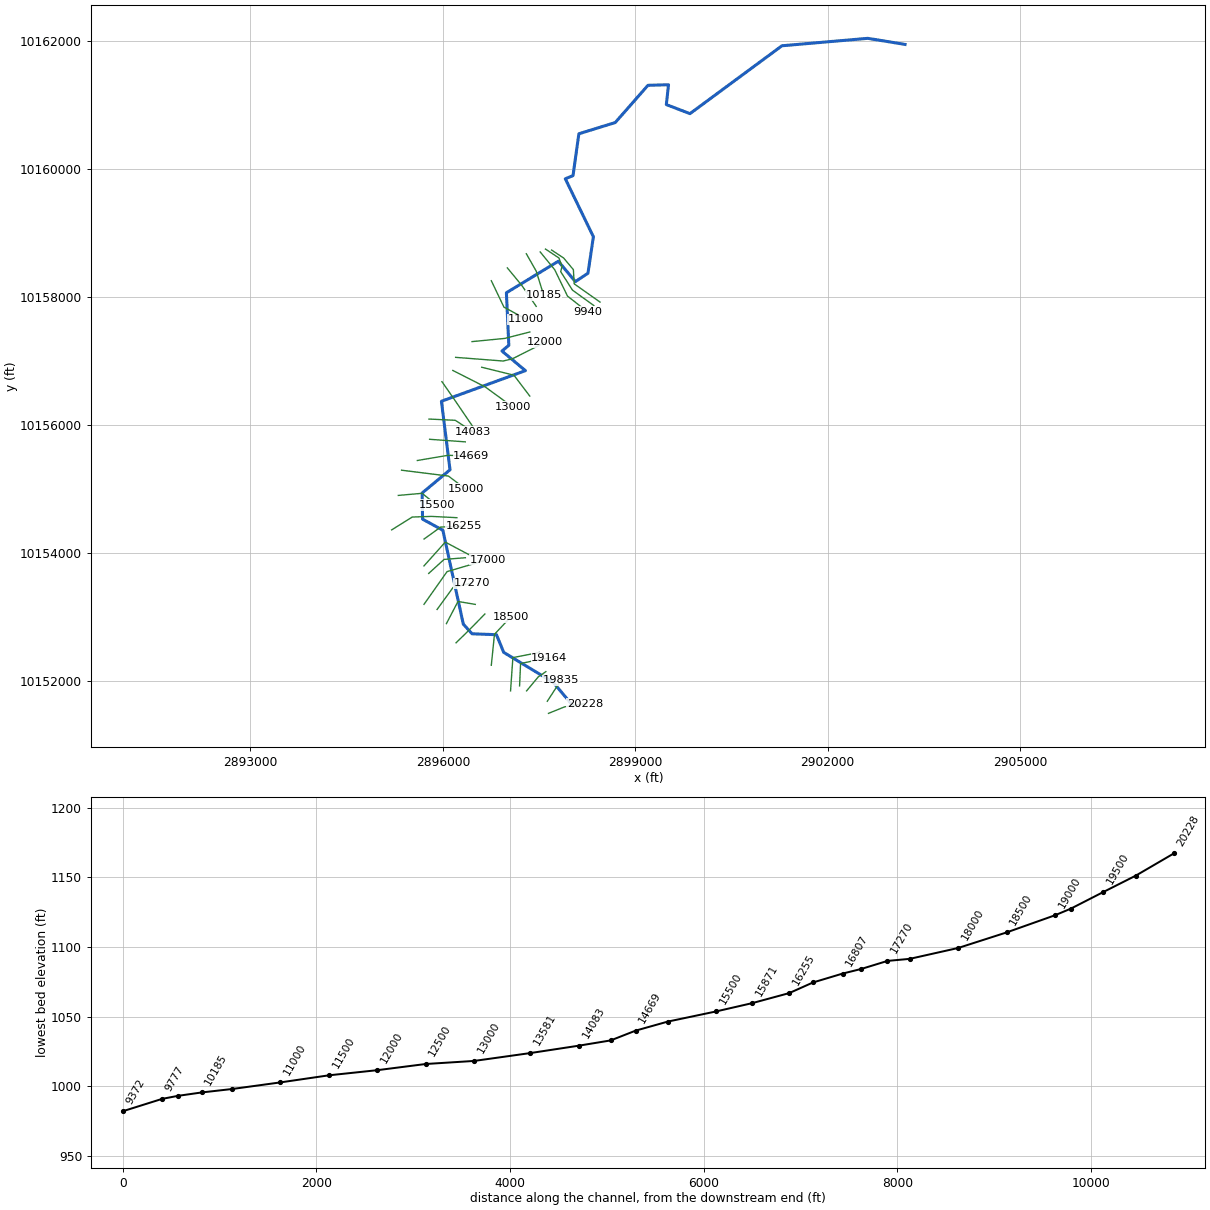
--- INKS 09.prj (project) ---

Proj Title=INKS 09 Base Level Engineering
Current Plan=p01
Default Exp/Contr=0.3,0.1
English Units
Geom File=g01
Flow File=f01
Plan File=p01
Y Axis Title=Elevation
X Axis Title(PF)=Main Channel Distance
X Axis Title(XS)=Station
BEGIN DESCRIPTION:
INKS 09
END DESCRIPTION:
DSS Export Rating Curves= 0
DSS Export Rating Curve Sorted= 0
DSS Export Volume Flow Curves= 0
DXF OffsetX= 0
DXF OffsetY= 0
DXF ScaleX= 1
DXF ScaleY= 10

--- INKS 09.p01 (plan) ---

Plan Title=Multiple Run
Short Identifier=Multiple
Geom File=g01
Flow File=f01
Subcritical Flow
K Sum by GR= 0
Std Step Tol= 0.01
Critical Tol= 0.01
Num of Std Step Trials= 20
Max Error Tol= 0.3
Flow Tol Ratio= 0.001
Split Flow NTrial= 30
Split Flow Tol= 0.02
Split Flow Ratio= 0.02
Log Output Level= 0
Friction Slope Method= 1
Unsteady Friction Slope Method= 2
Unsteady Bridges Friction Slope Method= 1
Parabolic Critical Depth
Global Vel Dist=  1 , 1 , 1
Global Log Level= 0
CheckData=True
Encroach Param= -1, 0, 0, 0
BEGIN DESCRIPTION:
Multiple Run
END DESCRIPTION:

--- INKS 09.f01 (steady flow) ---

Flow Title=Multiple
Program Version=4.10
Number of Profiles= 7
Profile Names=10-year,25-year,50-year,1pct_min,100-year,1pct_plu,500-year
River Rch & RM=INKS 09,Reach-1         ,20228
     547     904    1452    1053    2003    3809    2842
River Rch & RM=INKS 09,Reach-1         ,7000
     674    1123    1957    1465    2729    5082    3863
Boundary for River Rch & Prof#=INKS 09,Reach-1         , 1
Up Type= 0
Dn Type= 3
Dn Slope=0.005
Boundary for River Rch & Prof#=INKS 09,Reach-1         , 2
Up Type= 0
Dn Type= 3
Dn Slope=0.005
Boundary for River Rch & Prof#=INKS 09,Reach-1         , 3
Up Type= 0
Dn Type= 3
Dn Slope=0.005
Boundary for River Rch & Prof#=INKS 09,Reach-1         , 4
Up Type= 0
Dn Type= 3
Dn Slope=0.005
Boundary for River Rch & Prof#=INKS 09,Reach-1         , 5
Up Type= 0
Dn Type= 3
Dn Slope=0.005
Boundary for River Rch & Prof#=INKS 09,Reach-1         , 6
Up Type= 0
Dn Type= 3
Dn Slope=0.005
Boundary for River Rch & Prof#=INKS 09,Reach-1         , 7
Up Type= 0
Dn Type= 3
Dn Slope=0.005
DSS Import GetInterval= 0
DSS Import GetPeak= 0
DSS Import FillOption= 0

--- INKS 09.g01 (geometry) ---

Geom Title=Existing Conditions
Program Version=4.10

River Reach=INKS 09         ,Reach-1
Reach XY= 30
        2898029.       10151620.      2897722.75       10151985.
      2896949.25       10152454.      2896835.75       10152730.
      2896455.75       10152744.        2896319.       10152895.
        2896000.       10154360.       2895683.5       10154533.
       2895677.5       10154941.       2896111.5       10155303.
      2895977.75       10156372.      2897287.75       10156850.
      2896921.75       10157156.      2897028.75       10157245.
        2896991.       10158065.       2897800.5       10158557.
      2898066.25       10158239.        2898263.       10158370.
       2898347.5       10158939.       2897909.5       10159844.
      2898029.75       10159893.      2898121.25       10160546.
      2898688.25       10160721.       2899198.5       10161302.
      2899519.25       10161311.        2899485.       10161001.
      2899853.75       10160860.        2901288.       10161919.
        2902627.       10162035.       2903207.5       10161940.

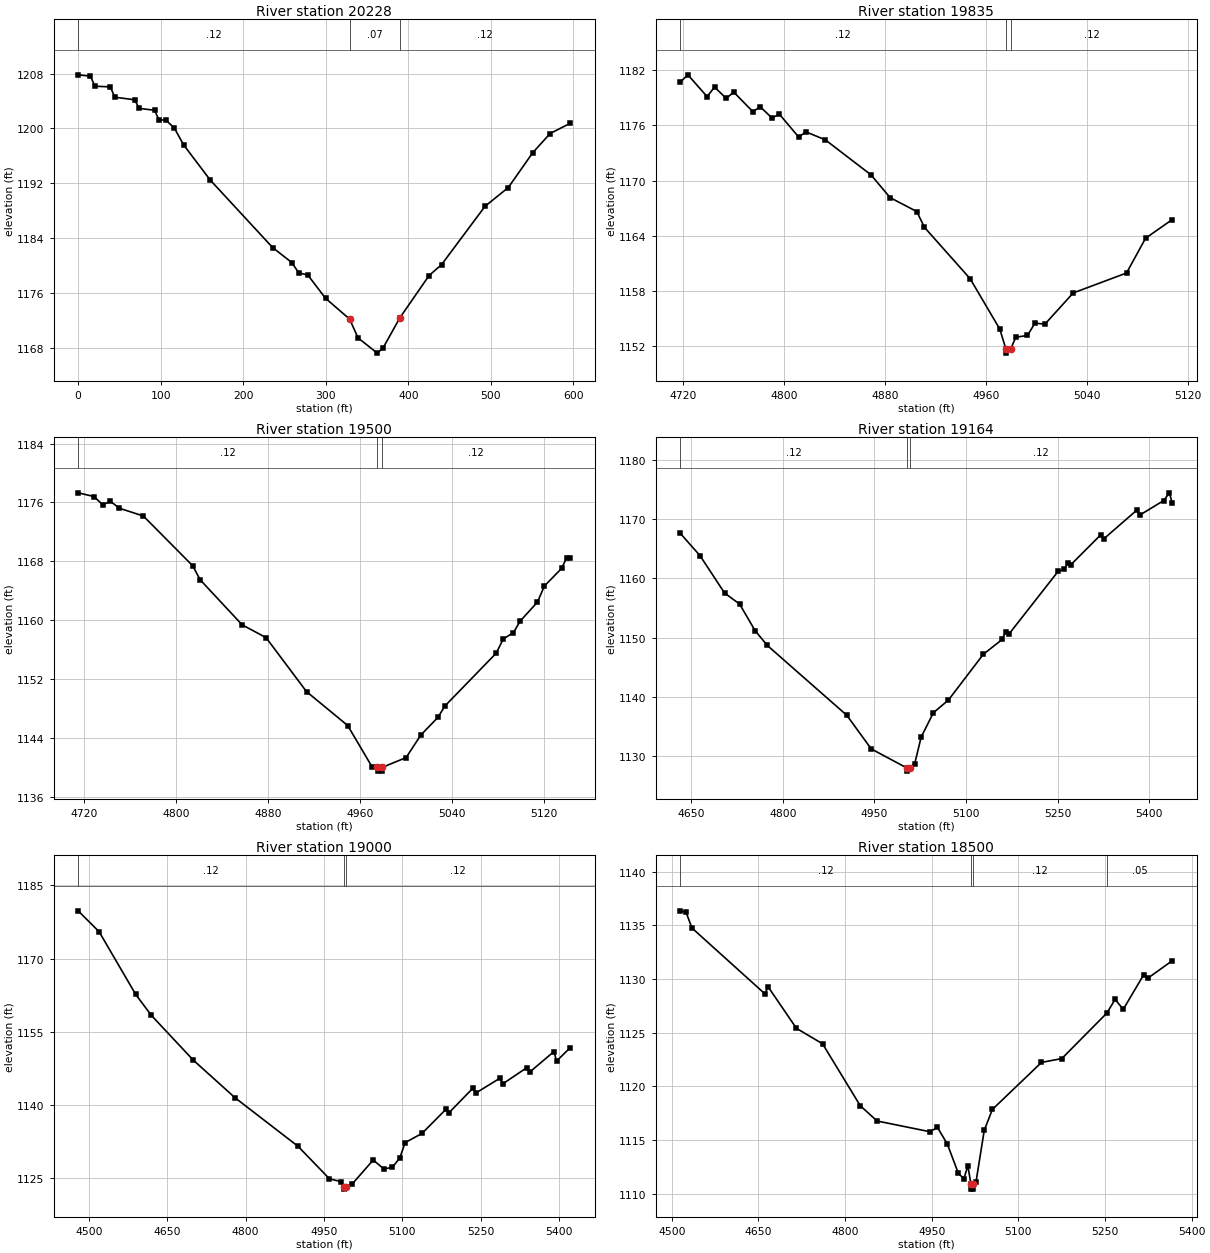
Type RM Length L Ch R = 1 ,20228   ,393,393,393
BEGIN DESCRIPTION:
INKS 09 39.0
END DESCRIPTION:
XS GIS Cut Line= 3
      2897647.32     10151502.36      2897899.41     10151604.45
      2898219.54     10151654.45
#Sta/Elev= 30
       0 1207.82    14.9 1207.62    20.3 1206.16      39 1206.06    44.4 1204.55
    68.5 1204.18    73.9 1202.92    92.6 1202.65      98 1201.21   106.1 1201.24
   116.7 1200.02   127.7 1197.61   160.1 1192.45   235.6 1182.61   258.8 1180.42
   267.3 1178.91   278.3 1178.59   299.7  1175.2   328.9 1172.16   339.1 1169.42
   362.4 1167.19   369.4 1167.94   389.7 1172.33   425.2 1178.52   440.3 1180.11
     493 1188.63   521.2 1191.37   550.7 1196.44   571.8 1199.25     596 1200.73
#Mann= 3 , 0 , 0
       0     .12       0   328.9     .07       0   389.7     .12       0
Bank Sta=328.9,389.7
XS Rating Curve= 0 ,0
Exp/Cntr=0.3,0.1

Type RM Length L Ch R = 1 ,19835   ,335,335,335
BEGIN DESCRIPTION:
Mapping XS 6748c9bf
END DESCRIPTION:
XS GIS Cut Line= 2
      2897628.62     10151691.19      2897841.02     10152017.56
#Sta/Elev= 30
  4718.1 1180.72  4724.1 1181.49  4739.3 1179.12  4745.2 1180.16  4754.4 1178.93
  4760.4 1179.61  4775.5 1177.49  4781.4 1178.01  4790.6 1176.81  4796.6  1177.2
  4811.7 1174.74  4817.7 1175.28  4832.8 1174.43    4869 1170.62  4884.2 1168.14
  4905.3 1166.63  4911.3 1164.92  4947.5 1159.33    4971 1153.85  4975.7 1151.74
    4976 1151.24  4979.7 1151.74  4983.7 1152.97  4992.9 1153.16  4998.8  1154.5
  5006.7 1154.39  5029.1 1157.78  5071.3 1159.95  5086.4 1163.73  5107.5 1165.76
#Mann= 3 ,-1 , 0
  4718.1     .12       0  4975.7     .07       0  4979.7     .12       0
Bank Sta=4975.7,4979.7
XS Rating Curve= 0 ,0
Exp/Cntr=0.3,0.1

Type RM Length L Ch R = 1 ,19500   ,336,336,336
BEGIN DESCRIPTION:
INKS 09 38.0
END DESCRIPTION:
XS GIS Cut Line= 3
      2897305.65     10151853.08      2897488.27     10152072.14
      2897605.66      10152153.1
#Sta/Elev= 30
  4714.8 1177.31  4728.5 1176.81  4736.3 1175.67  4742.8 1176.17  4750.6 1175.22
  4771.5 1174.16  4814.4  1167.4  4820.9 1165.49  4857.4 1159.37  4878.2 1157.63
  4913.4 1150.29  4949.2 1145.68  4970.6 1140.01  4975.1 1139.98  4975.4 1139.48
  4978.9 1139.48  4979.1 1139.98    5000 1141.32  5012.8 1144.38  5027.7 1146.79
  5033.8 1148.34  5078.4 1155.52  5084.5 1157.45  5093.3  1158.3  5099.3 1159.89
  5114.2 1162.45  5120.3 1164.65  5135.2 1167.03  5139.6 1168.46  5142.6 1168.46
#Mann= 3 ,-1 , 0
  4714.8     .12       0  4975.1     .07       0  4979.1     .12       0
Bank Sta=4975.1,4979.1
XS Rating Curve= 0 ,0
Exp/Cntr=0.3,0.1

Type RM Length L Ch R = 1 ,19164   ,164,164,164
BEGIN DESCRIPTION:
Mapping XS 7c172ecc
END DESCRIPTION:
XS GIS Cut Line= 4
      2897196.35     10151930.82      2897211.98     10152279.76
      2897456.77     10152331.84      2897659.37      10152368.2
#Sta/Elev= 30
  4632.2 1167.56  4664.5  1163.8  4704.6 1157.52  4729.3 1155.65  4754.6 1151.18
  4774.6 1148.69  4904.8 1136.92  4944.8 1131.26  5003.7 1128.02    5004 1127.52
  5007.7 1128.02    5016  1128.8  5026.5 1133.25  5046.6 1137.37  5070.9 1139.46
  5128.4 1147.21  5159.1 1149.69    5165 1151.03  5170.1 1150.58    5251  1161.2
  5261.1 1161.52  5266.7 1162.61  5271.8  1162.3  5320.4 1167.31  5325.5 1166.64
  5379.2 1171.44  5384.3 1170.63  5423.7 1173.09  5432.9 1174.39  5437.6 1172.68
#Mann= 3 ,-1 , 0
  4632.2     .12       0  5003.7     .07       0  5007.7     .12       0
Bank Sta=5003.7,5007.7
XS Rating Curve= 0 ,0
Exp/Cntr=0.3,0.1

Type RM Length L Ch R = 1 ,19000   ,500,500,500
BEGIN DESCRIPTION:
INKS 09 37.0
END DESCRIPTION:
XS GIS Cut Line= 3
      2897055.68     10151853.11      2897092.09     10152372.43
       2897505.7     10152453.11
#Sta/Elev= 30
  4479.4 1179.77  4519.5  1175.5  4589.7 1162.63  4619.7 1158.34  4699.9 1149.18
  4780.1 1141.45  4900.4 1131.53  4960.6 1124.87  4982.8 1124.28  4988.7 1123.25
  4988.9 1122.75  4992.7 1123.25  5004.4 1123.82  5044.4 1128.71  5064.8 1126.89
    5081  1127.2  5095.4 1129.15  5105.5 1132.28  5137.7 1134.15  5184.2 1139.16
  5189.3 1138.37  5235.7 1143.47  5240.8 1142.43  5287.3 1145.49  5292.4 1144.31
  5338.9 1147.66    5344 1146.72  5390.5 1150.93  5395.6 1148.99  5421.4  1151.7
#Mann= 3 ,-1 , 0
  4479.4     .12       0  4988.7     .07       0  4992.7     .12       0
Bank Sta=4988.7,4992.7
XS Rating Curve= 0 ,0
Exp/Cntr=0.3,0.1

Type RM Length L Ch R = 1 ,18500   ,500,500,500
BEGIN DESCRIPTION:
INKS 09 36.0
END DESCRIPTION:
XS GIS Cut Line= 3
      2896755.69     10152253.15      2896804.96     10152735.95
      2897055.69     10153003.12
#Sta/Elev= 30
  4514.7 1136.36  4524.7 1136.22  4534.8 1134.76  4661.4 1128.61  4666.4  1129.3
  4715.7 1125.41  4760.9 1123.97  4826.3 1118.19  4855.4 1116.77  4946.9 1115.77
  4959.9 1116.17    4977 1114.62  4996.1 1111.89  5005.7 1111.39  5012.5  1112.6
  5017.8 1110.92  5018.1 1110.42  5021.6 1110.42  5021.8 1110.92  5026.7 1111.12
  5040.9  1115.9    5055 1117.85    5140 1122.23  5175.2 1122.59    5253 1126.82
  5267.5  1128.1  5281.6 1127.18  5316.8 1130.39  5324.1 1130.08  5366.4 1131.71
#Mann= 4 ,-1 , 0
  4514.7     .12       0  5017.8     .07       0  5021.8     .12       0
    5253     .05       0
Bank Sta=5017.8,5021.8
XS Rating Curve= 0 ,0
Exp/Cntr=0.3,0.1

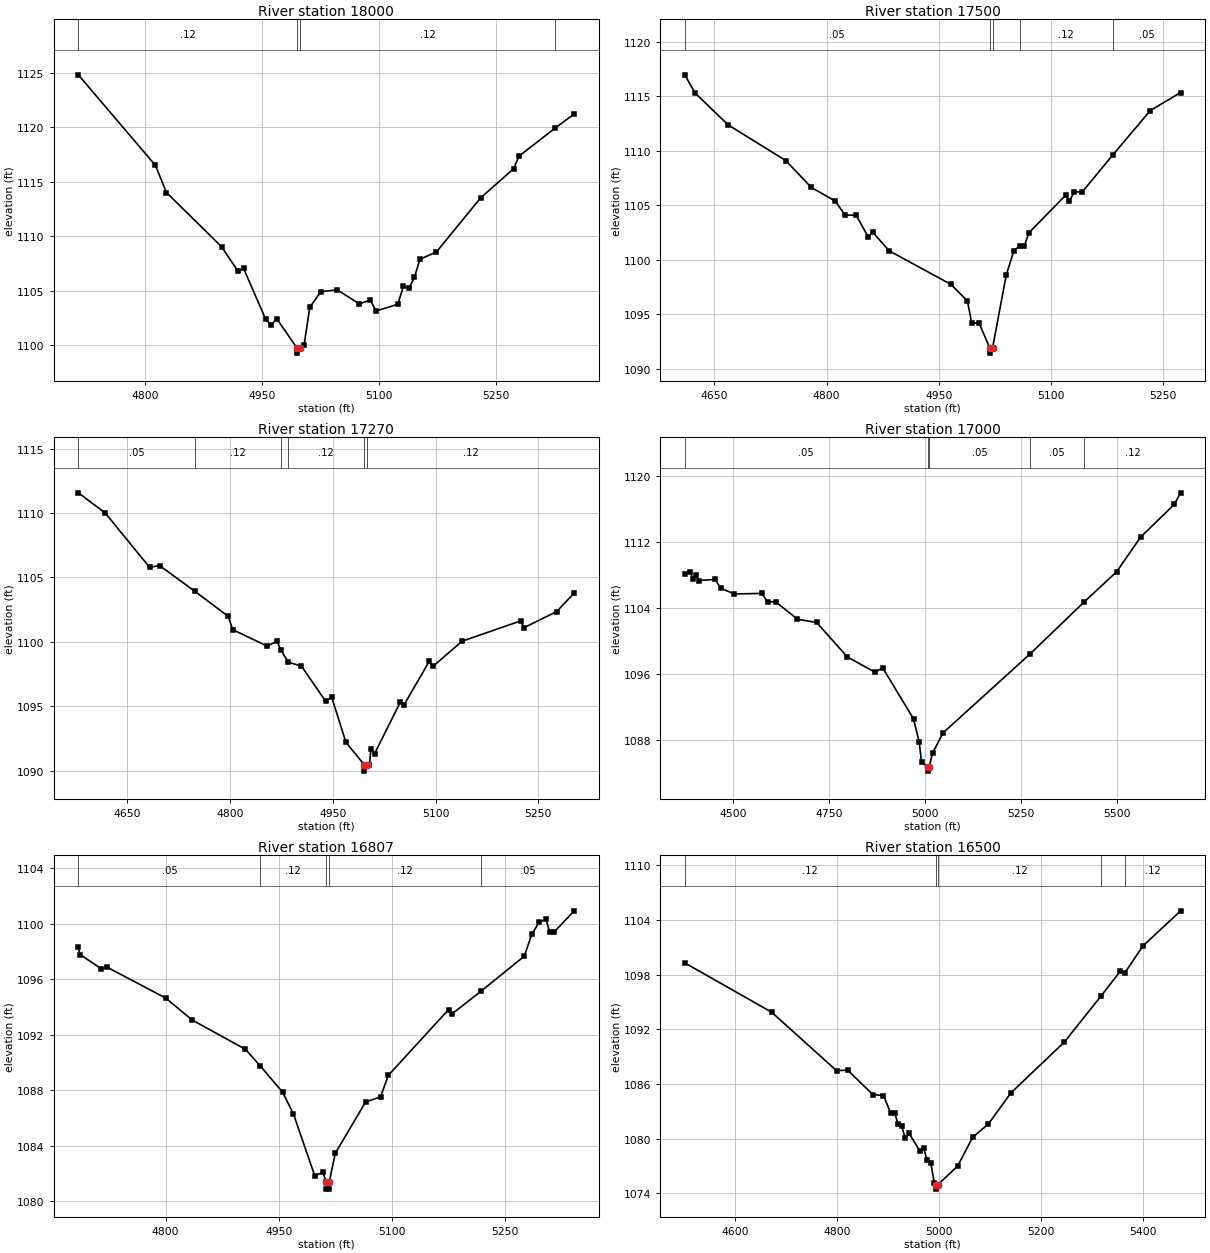
Type RM Length L Ch R = 1 ,18000   ,500,500,500
BEGIN DESCRIPTION:
INKS 09 35.0
END DESCRIPTION:
XS GIS Cut Line= 3
      2896205.65     10152603.08      2896410.04     10152802.56
       2896655.7     10153053.13
#Sta/Elev= 30
  4714.4 1124.81  4813.4 1116.49  4827.5    1114  4898.2 1109.03  4919.5 1106.75
  4926.5 1107.03  4954.8 1102.38    4962 1101.81    4969 1102.42  4994.8 1099.75
  4995.1 1099.25  4998.8 1099.75  5004.3 1100.04  5011.5 1103.45  5025.6 1104.89
  5046.8 1105.06  5075.1 1103.78  5089.2 1104.12  5096.4 1103.12  5124.6 1103.74
  5131.6 1105.37  5138.8  1105.2  5145.8 1106.21  5152.9 1107.87  5174.1 1108.54
  5230.7  1113.5  5273.1 1116.18  5280.2 1117.35  5326.9 1119.94  5350.9 1121.21
#Mann= 4 ,-1 , 0
  4714.4     .12       0  4994.8     .07       0  4998.8     .12       0
  5326.9     .05       0
Bank Sta=4994.8,4998.8
XS Rating Curve= 0 ,0
Exp/Cntr=0.3,0.1

Type RM Length L Ch R = 1 ,17500   ,230,230,230
BEGIN DESCRIPTION:
INKS 09 34.0
END DESCRIPTION:
XS GIS Cut Line= 3
      2896055.69     10152903.12      2896235.98      10153248.6
      2896505.67     10153203.11
#Sta/Elev= 30
  4610.3 1116.95  4624.2 1115.27  4668.3 1112.36  4745.4 1109.09  4779.5 1106.63
  4811.7 1105.37  4824.6 1104.09  4839.4 1104.08  4855.8 1102.09  4861.5 1102.54
  4883.6 1100.82  4966.3 1097.74  4988.4 1096.22    4994  1094.2  5003.9  1094.2
    5018 1091.94  5018.2 1091.44    5022 1091.94  5040.3 1098.61  5050.4 1100.81
  5058.1 1101.29  5064.3 1101.26  5070.7 1102.48  5119.8 1105.92  5124.8 1105.41
  5131.5 1106.23  5141.7  1106.2  5182.6 1109.59  5232.9 1113.67  5273.5 1115.33
#Mann= 5 ,-1 , 0
  4610.3     .05       0    5018     .05       0    5022     .05       0
  5058.1     .12       0  5182.6     .05       0
Bank Sta=5018,5022
XS Rating Curve= 0 ,0
Exp/Cntr=0.3,0.1

Type RM Length L Ch R = 1 ,17270   ,270,270,270
BEGIN DESCRIPTION:
Mapping XS 3fd82233
END DESCRIPTION:
XS GIS Cut Line= 3
      2895909.91     10153123.52      2896159.89     10153467.26
      2896451.12     10153534.86
#Sta/Elev= 30
  4578.4 1111.57  4617.4 1110.02  4682.4 1105.79    4697 1105.92  4748.7 1103.92
  4797.5 1101.97  4803.7 1100.95  4853.9 1099.67  4868.6 1100.04  4874.1 1099.37
    4885 1098.42  4904.2 1098.11  4939.7 1095.37  4948.2 1095.73  4969.1  1092.2
  4995.8 1090.46    4996 1089.96  4999.8 1090.46  5003.4 1090.46  5005.7 1091.68
  5010.9 1091.31  5048.4  1095.3  5053.5 1095.06    5091  1098.5  5096.1 1098.09
  5138.8 1100.05  5224.1 1101.62  5229.2  1101.1    5277 1102.35  5302.4 1103.79
#Mann= 6 ,-1 , 0
  4578.4     .05       0  4748.7     .12       0  4874.1     .05       0
    4885     .12       0  4995.8     .07       0  4999.8     .12       0
Bank Sta=4995.8,4999.8
XS Rating Curve= 0 ,0
Exp/Cntr=0.3,0.1

Type RM Length L Ch R = 1 ,17000   ,193,193,193
BEGIN DESCRIPTION:
INKS 09 33.0
END DESCRIPTION:
XS GIS Cut Line= 3
      2895705.66     10153203.08       2896065.9     10153714.06
      2896705.65      10153903.1
#Sta/Elev= 30
  4374.8 1108.18  4388.4 1108.34    4397 1107.46  4403.2 1107.99  4411.5 1107.33
  4453.7 1107.46  4468.5  1106.4  4504.2 1105.69  4575.6 1105.77  4590.4 1104.74
  4611.3 1104.76  4668.5 1102.63  4718.4 1102.24  4798.5 1098.05  4869.9 1096.22
  4890.8 1096.72  4970.9 1090.54  4985.7 1087.74  4991.8  1085.3  5007.6  1084.7
  5007.9  1084.2  5011.6  1084.7  5020.6  1086.4  5048.1 1088.85  5274.9 1098.43
  5416.5 1104.76  5500.3 1108.39  5562.9  1112.6  5650.5 1116.56  5667.1 1117.97
#Mann= 5 ,-1 , 0
  4374.8     .05       0  5007.6     .03       0  5011.6     .05       0
  5274.9     .05       0  5416.5     .12       0
Bank Sta=5007.6,5011.6
XS Rating Curve= 0 ,0
Exp/Cntr=0.3,0.1

Type RM Length L Ch R = 1 ,16807   ,307,307,307
BEGIN DESCRIPTION:
Mapping XS 8292fb10
END DESCRIPTION:
XS GIS Cut Line= 3
      2895779.65     10153685.97      2896019.27     10153904.76
      2896351.68     10153930.73
#Sta/Elev= 30
  4684.2 1098.28  4686.5 1097.77  4714.9 1096.74  4721.6 1096.88    4800 1094.64
  4835.1 1093.06    4906 1090.94  4925.7 1089.74  4955.4 1087.84  4969.6 1086.29
  4997.9 1081.83  5008.7 1082.08  5013.1 1081.37  5013.4 1080.87  5016.9 1080.87
  5017.1 1081.37  5025.1 1083.45  5065.3 1087.14  5085.3 1087.52  5095.4 1089.06
  5175.4  1093.8  5180.4 1093.51    5219 1095.15  5275.9 1097.65  5285.9 1099.23
    5296 1100.13  5304.8  1100.3  5309.8 1099.36    5316 1099.42  5342.1 1100.92
#Mann= 5 ,-1 , 0
  4684.2     .05       0  4925.7     .12       0  5013.1     .07       0
  5017.1     .12       0    5219     .05       0
Bank Sta=5013.1,5017.1
XS Rating Curve= 0 ,0
Exp/Cntr=0.3,0.1

Type RM Length L Ch R = 1 ,16500   ,245,245,245
BEGIN DESCRIPTION:
INKS 09 32.0
END DESCRIPTION:
XS GIS Cut Line= 3
      2895705.69     10153803.11       2896037.7     10154174.56
      2896455.67     10153953.12
#Sta/Elev= 30
  4501.8  1099.3  4671.9 1093.89    4799 1087.47  4820.7 1087.53    4870 1084.85
    4891 1084.73  4905.2 1082.81  4912.7 1082.86  4919.4 1081.63  4926.9 1081.34
  4933.6 1080.03  4941.1 1080.59    4962 1078.66  4969.5 1079.01  4976.2 1077.69
  4983.7 1077.33  4990.4 1075.17  4993.7 1074.96  4993.9 1074.46  4997.7 1074.96
  5036.2 1076.99  5065.6 1080.15  5096.6 1081.62  5140.6 1085.03  5244.9 1090.59
  5317.1 1095.66  5354.9  1098.4  5363.9 1098.22  5398.9 1101.15    5473 1105.02
#Mann= 5 ,-1 , 0
  4501.8     .12       0  4993.7     .07       0  4997.7     .12       0
  5317.1     .05       0  5363.9     .12       0
Bank Sta=4993.7,4997.7
XS Rating Curve= 0 ,0
Exp/Cntr=0.3,0.1

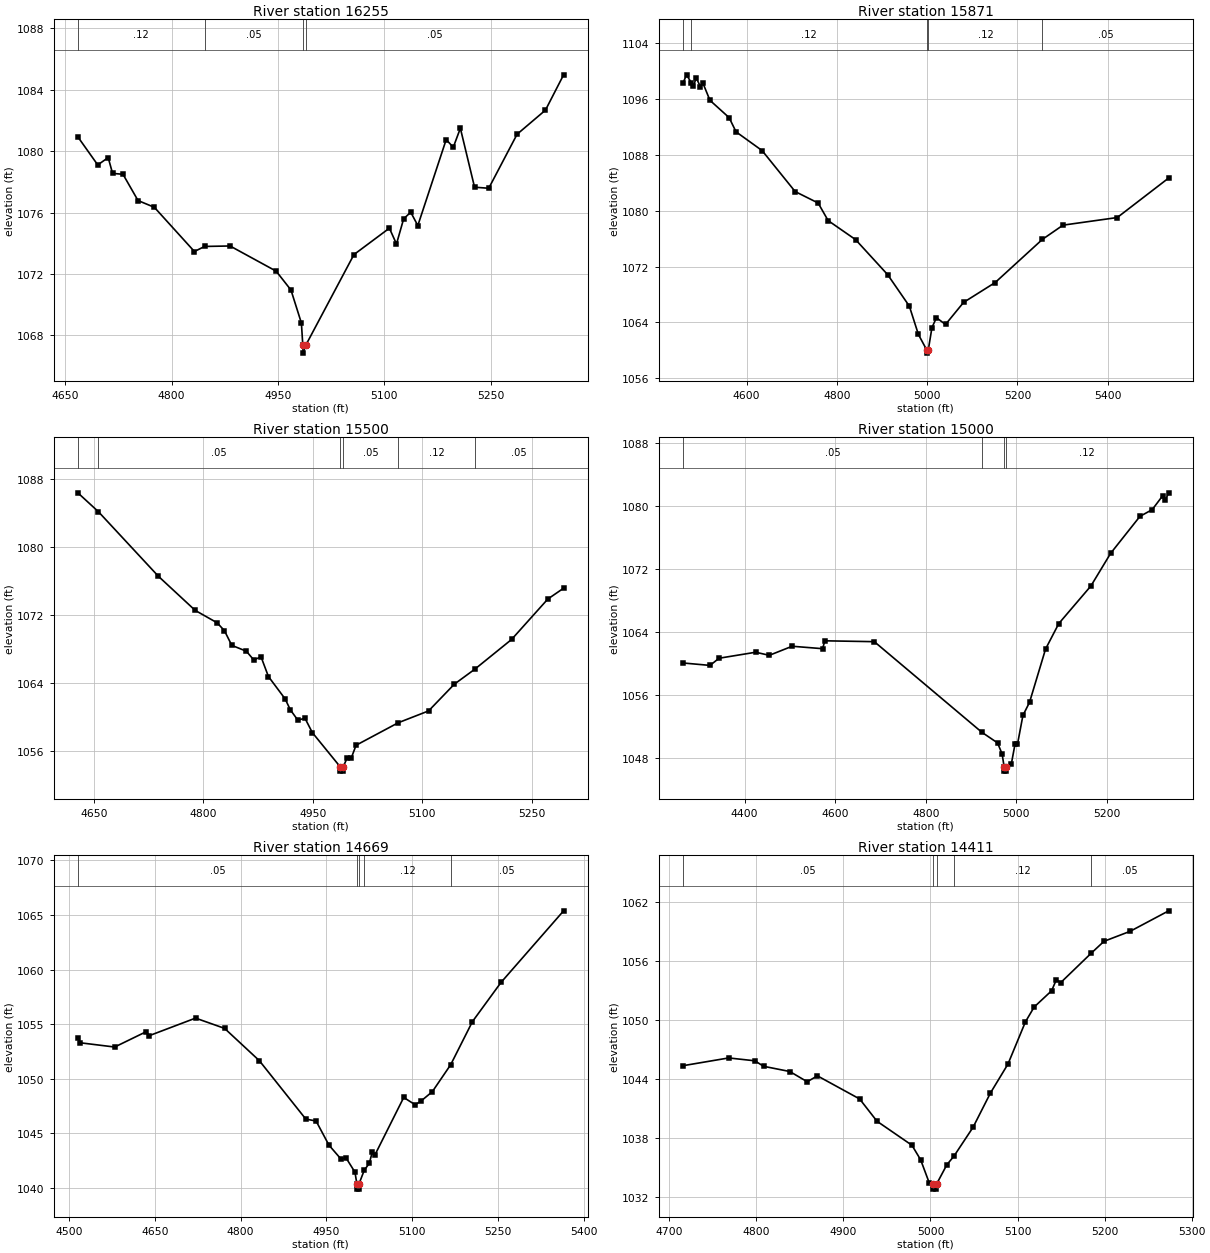
Type RM Length L Ch R = 1 ,16255   ,384,384,384
BEGIN DESCRIPTION:
Mapping XS 992727ae
END DESCRIPTION:
XS GIS Cut Line= 3
      2895706.77     10154222.46      2895967.18     10154409.96
      2896331.24     10154420.37
#Sta/Elev= 30
  4667.8 1080.93  4695.9  1079.1  4710.6 1079.58  4716.8 1078.55  4731.5 1078.49
  4752.7 1076.78  4775.7 1076.34  4832.2 1073.46  4846.6 1073.79  4882.5 1073.82
  4947.5 1072.18  4968.4 1070.95  4983.1  1068.8  4985.1 1067.34  4985.4 1066.84
  4989.1 1067.34  5057.2 1073.26  5107.2 1074.98  5117.2 1073.95  5127.3 1075.59
  5137.3 1076.02  5147.3 1075.15  5187.3 1080.75  5197.3 1080.25  5207.3 1081.49
  5227.3 1077.65  5247.3 1077.58  5287.3  1081.1  5327.3 1082.67  5352.9 1084.97
#Mann= 4 ,-1 , 0
  4667.8     .12       0  4846.6     .05       0  4985.1     .03       0
  4989.1     .05       0
Bank Sta=4985.1,4989.1
XS Rating Curve= 0 ,0
Exp/Cntr=0.3,0.1

Type RM Length L Ch R = 1 ,15871   ,371,371,371
BEGIN DESCRIPTION:
Mapping XS 61f99ba0
END DESCRIPTION:
XS GIS Cut Line= 4
      2895201.71      10154365.2      2895522.55     10154565.72
      2895823.35     10154575.74      2896219.43     10154555.69
#Sta/Elev= 30
  4459.1 1098.22  4467.1 1099.44  4477.9 1098.29  4482.5 1097.77  4488.4 1099.03
  4497.8 1097.75  4503.7 1098.21    4519 1095.79  4561.5 1093.31  4576.8 1091.28
  4634.6 1088.59  4707.7 1082.73  4758.6 1081.09  4780.8 1078.57  4841.5 1075.85
  4912.5 1070.84  4960.6 1066.33  4980.7 1062.27  4998.7  1060.1  4998.9  1059.6
  5002.7  1060.1  5010.7 1063.26  5020.7 1064.67  5040.7  1063.7  5080.7 1066.86
  5150.8 1069.71  5255.4 1075.89    5301 1077.92  5421.1 1079.01    5535 1084.67
#Mann= 5 ,-1 , 0
  4459.1     .05       0  4477.9     .12       0  4998.7     .07       0
  5002.7     .12       0  5255.4     .05       0
Bank Sta=4998.7,5002.7
XS Rating Curve= 0 ,0
Exp/Cntr=0.3,0.1

Type RM Length L Ch R = 1 ,15500   ,500,500,500
BEGIN DESCRIPTION:
INKS 09 30.0
END DESCRIPTION:
XS GIS Cut Line= 3
      2895305.66     10154903.11      2895676.09      10154936.1
      2895905.69     10154753.11
#Sta/Elev= 30
  4628.1 1086.35  4656.1 1084.15  4738.6 1076.54  4788.8 1072.55  4818.9 1071.09
  4828.9 1070.17    4839 1068.44    4859 1067.75  4869.1 1066.73  4879.1 1067.09
  4889.2 1064.78  4912.1 1062.15  4919.3 1060.86  4929.3 1059.68  4939.4 1059.86
  4949.4 1058.19  4987.6 1054.17  4987.8 1053.67  4991.3 1053.67  4991.6 1054.17
  4997.3 1055.26  5002.9 1055.26  5009.3 1056.71    5067 1059.35  5108.6 1060.74
  5143.9 1063.88  5172.1 1065.65  5222.3 1069.13    5272 1073.88  5293.6 1075.15
#Mann= 6 ,-1 , 0
  4628.1     .12       0  4656.1     .05       0  4987.6     .05       0
  4991.6     .05       0    5067     .12       0  5172.1     .05       0
Bank Sta=4987.6,4991.6
XS Rating Curve= 0 ,0
Exp/Cntr=0.3,0.1

Type RM Length L Ch R = 1 ,15000   ,331,331,331
BEGIN DESCRIPTION:
INKS 09 29.0
END DESCRIPTION:
XS GIS Cut Line= 3
      2895356.37     10155296.61      2896086.87      10155205.2
      2896355.68     10155003.11
#Sta/Elev= 30
  4263.8 1060.07  4323.6 1059.76  4343.7 1060.67  4424.4 1061.43  4454.6 1061.04
    4505 1062.19  4572.2 1061.88  4577.2 1062.88  4686.4 1062.77  4923.8 1051.28
  4958.5 1049.93  4968.6 1048.52  4973.1 1046.85  4973.3 1046.35  4976.8 1046.35
  4977.1 1046.85  4988.7  1047.2  4996.9 1049.73  5002.4 1049.73  5014.5 1053.42
  5029.1 1055.08  5064.5 1061.84  5093.7 1065.07  5164.5 1069.83  5208.2 1073.98
  5272.8 1078.66  5299.9 1079.52  5322.8 1081.26    5329 1080.74  5336.3 1081.65
#Mann= 4 ,-1 , 0
  4263.8     .05       0  4923.8     .12       0  4973.1     .07       0
  4977.1     .12       0
Bank Sta=4973.1,4977.1
XS Rating Curve= 0 ,0
Exp/Cntr=0.3,0.1

Type RM Length L Ch R = 1 ,14669   ,258,258,258
BEGIN DESCRIPTION:
INKS 09 28.0
END DESCRIPTION:
XS GIS Cut Line= 3
       2895602.8      10155448.1       2896080.5       10155529.
      2896445.04     10155518.28
#Sta/Elev= 30
  4515.5 1053.76  4519.5 1053.29  4579.9  1052.9  4635.2 1054.31  4640.3 1053.94
  4721.3 1055.55    4772 1054.61  4832.8 1051.65    4914  1046.3    4932 1046.12
  4954.5 1043.91  4974.8 1042.68    4985 1042.69    5000 1041.43  5003.2 1040.38
  5003.4 1039.88  5006.9 1039.88  5007.2 1040.38  5016.1  1041.6  5025.2 1042.26
  5030.2 1043.29  5035.2 1043.05  5085.2 1048.28  5105.2 1047.61  5115.2 1047.94
  5135.2 1048.81  5167.3 1051.28  5205.3 1055.23  5255.3 1058.82  5364.7 1065.38
#Mann= 5 ,-1 , 0
  4515.5     .05       0  5003.2     .03       0  5007.2     .05       0
  5016.1     .12       0  5167.3     .05       0
Bank Sta=5003.2,5007.2
XS Rating Curve= 0 ,0
Exp/Cntr=0.3,0.1

Type RM Length L Ch R = 1 ,14411   ,328,328,328
BEGIN DESCRIPTION:
Mapping XS cd676246
END DESCRIPTION:
XS GIS Cut Line= 2
      2895793.25     10155778.98      2896349.81     10155738.87
#Sta/Elev= 30
  4715.6  1045.4  4768.2 1046.19  4798.2  1045.9  4808.3 1045.34  4838.4 1044.81
  4858.4 1043.77  4870.1 1044.37  4918.6 1042.02  4938.6 1039.75  4978.7 1037.31
  4988.7 1035.83  4998.8 1033.43  5002.9 1033.35  5003.1 1032.85  5006.6 1032.85
  5006.9 1033.35  5018.8 1035.33    5027 1036.21  5048.9 1039.14  5068.9 1042.63
    5089 1045.57  5109.1 1049.87  5119.1 1051.37  5139.1 1053.02  5144.6 1054.15
  5149.6 1053.85  5184.6 1056.84  5199.3 1058.05  5229.4 1059.07  5273.6 1061.15
#Mann= 5 ,-1 , 0
  4715.6     .05       0  5002.9     .05       0  5006.9     .05       0
    5027     .12       0  5184.6     .05       0
Bank Sta=5002.9,5006.9
XS Rating Curve= 0 ,0
Exp/Cntr=0.3,0.1

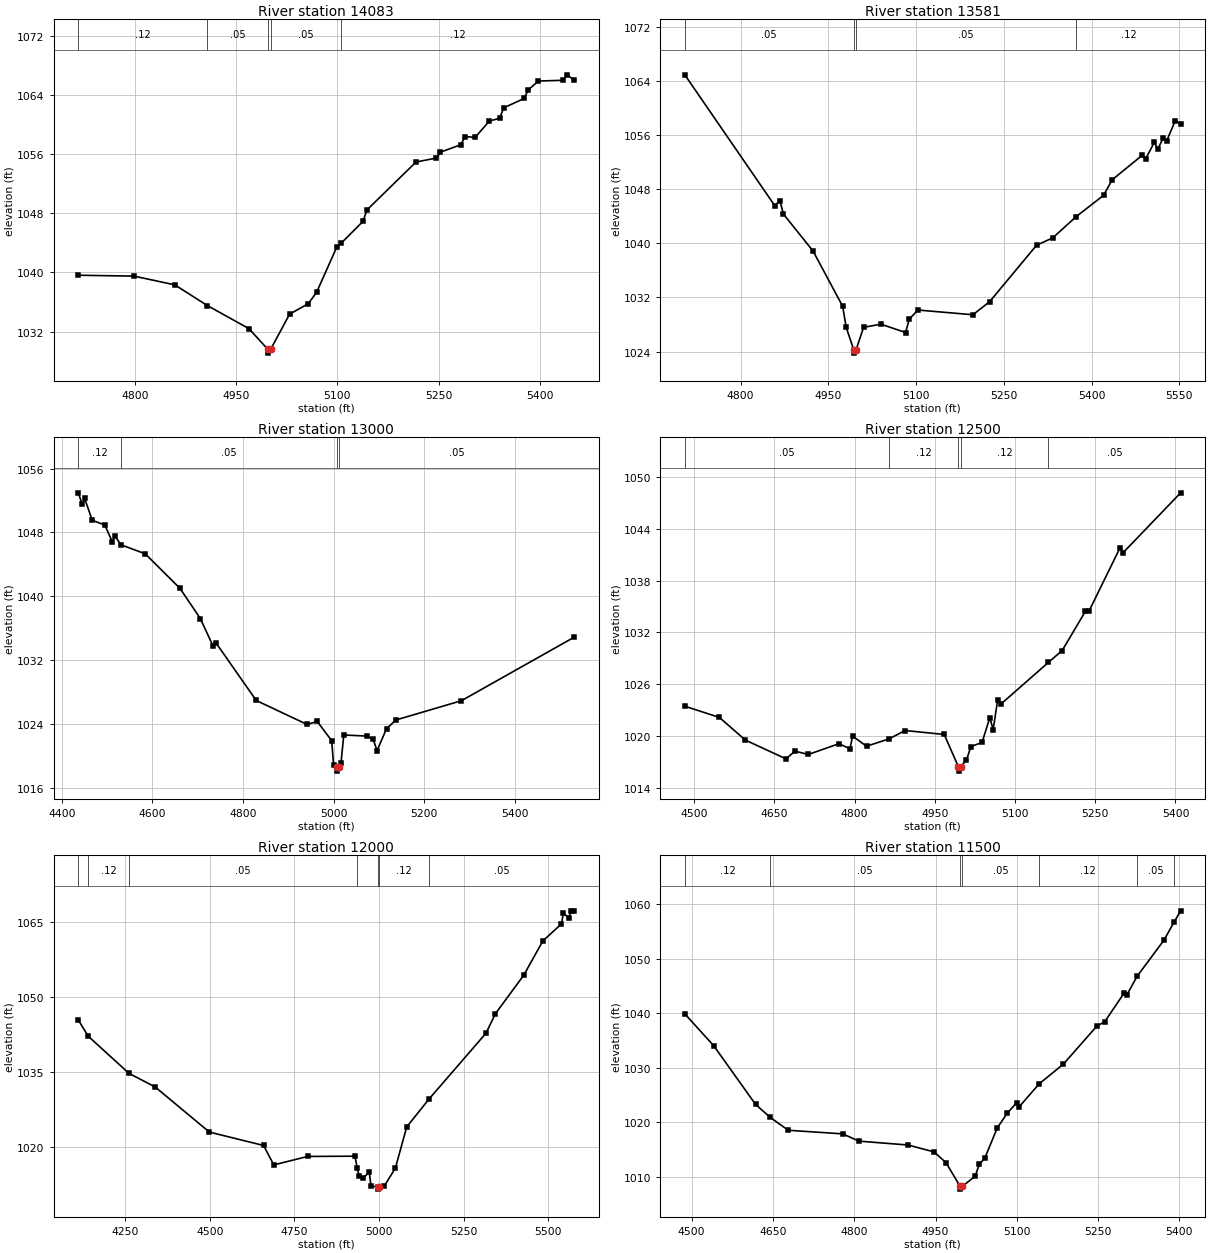
Type RM Length L Ch R = 1 ,14083   ,502,502,502
BEGIN DESCRIPTION:
Mapping XS 533d31fe
END DESCRIPTION:
XS GIS Cut Line= 3
      2895783.27     10156094.83      2896194.35     10156074.78
      2896465.09      10155899.3
#Sta/Elev= 30
  4716.5 1039.62    4799  1039.5  4859.3 1038.32  4907.5 1035.52  4969.2 1032.39
  4997.2 1029.58  4997.5 1029.08  5001.2 1029.58  5029.3 1034.35    5057 1035.77
  5069.3 1037.31  5099.4 1043.47  5105.5 1043.94    5138 1046.91  5143.9 1048.46
  5216.5 1054.94  5246.8 1055.48  5252.7 1056.27    5283 1057.29    5289 1058.38
  5304.1 1058.28  5325.2 1060.49  5340.4 1060.86  5346.3 1062.27  5376.6 1063.54
  5382.6  1064.7  5397.8  1065.9    5434    1066    5440 1066.74  5450.7 1066.04
#Mann= 5 ,-1 , 0
  4716.5     .12       0  4907.5     .05       0  4997.2     .05       0
  5001.2     .05       0  5105.5     .12       0
Bank Sta=4997.2,5001.2
XS Rating Curve= 0 ,0
Exp/Cntr=0.3,0.1

Type RM Length L Ch R = 1 ,13581   ,581,581,581
BEGIN DESCRIPTION:
INKS 09 26.0
END DESCRIPTION:
XS GIS Cut Line= 3
      2895985.52     10156678.26      2896164.78     10156421.18
      2896465.09     10155979.51
#Sta/Elev= 30
  4704.7 1064.95  4858.5 1045.58  4867.2 1046.34  4873.3 1044.34  4923.9 1038.87
  4974.5  1030.7  4980.6 1027.56  4993.5 1024.26  4993.7 1023.76  4997.5 1024.26
  5010.3 1027.58    5040 1028.04  5082.1 1026.81  5088.3 1028.78  5103.1 1030.14
  5197.2 1029.44  5225.8 1031.38    5306 1039.73  5333.6 1040.82  5373.8 1043.97
  5420.4 1047.11  5435.3 1049.42  5486.2 1053.02  5492.2 1052.47  5507.2 1054.96
  5513.2 1053.97  5522.1 1055.53  5528.1 1055.12  5543.1 1058.18  5552.2 1057.74
#Mann= 4 ,-1 , 0
  4704.7     .05       0  4993.5     .05       0  4997.5     .05       0
  5373.8     .12       0
Bank Sta=4993.5,4997.5
XS Rating Curve= 0 ,0
Exp/Cntr=0.3,0.1

Type RM Length L Ch R = 1 ,13000   ,500,500,500
BEGIN DESCRIPTION:
INKS 09 25.0
END DESCRIPTION:
XS GIS Cut Line= 3
      2896155.71      10156853.1      2896658.07     10156597.83
      2897086.77     10156285.34
#Sta/Elev= 30
  4436.5 1052.97  4444.8 1051.55  4450.4 1052.28  4467.1 1049.53  4494.9 1048.94
  4511.6 1046.81  4517.2 1047.61  4530.1 1046.46  4583.9 1045.34  4660.8    1041
  4705.7 1037.22  4734.1 1033.73  4739.7 1034.21  4829.1 1026.95  4941.2 1023.95
  4963.7 1024.32  4995.5 1021.91  4999.7 1018.87  5007.4  1018.6  5007.7  1018.1
  5011.4  1018.6  5016.1 1019.16  5022.2 1022.63  5072.5 1022.49  5087.1 1022.09
  5095.6 1020.67  5116.5 1023.42  5137.3 1024.51  5281.7 1026.92  5530.5 1034.88
#Mann= 4 ,-1 , 0
  4436.5     .12       0  4530.1     .05       0  5007.4     .05       0
  5011.4     .05       0
Bank Sta=5007.4,5011.4
XS Rating Curve= 0 ,0
Exp/Cntr=0.3,0.1

Type RM Length L Ch R = 1 ,12500   ,500,500,500
BEGIN DESCRIPTION:
INKS 09 24.0
END DESCRIPTION:
XS GIS Cut Line= 3
      2896605.73      10156903.1      2897108.12     10156779.38
      2897355.71     10156453.08
#Sta/Elev= 30
  4482.6 1023.43  4547.4 1022.12  4595.8  1019.5  4671.9 1017.32  4688.5 1018.22
  4713.4 1017.83  4770.9 1019.08  4791.3 1018.49  4796.4 1019.95  4822.4 1018.79
  4864.2 1019.63  4894.5 1020.61  4967.6 1020.15  4994.2  1016.4  4994.4  1015.9
  4998.2  1016.4  5009.2 1017.18  5017.5 1018.75  5038.3 1019.22  5052.8 1022.09
  5059.1 1020.72  5067.4  1024.1  5073.7 1023.68  5162.3  1028.5  5188.1 1029.88
  5231.7 1034.44    5238 1034.42  5296.2 1041.78  5302.4 1041.25  5409.6 1048.17
#Mann= 5 ,-1 , 0
  4482.6     .05       0  4864.2     .12       0  4994.2     .07       0
  4998.2     .12       0  5162.3     .05       0
Bank Sta=4994.2,4998.2
XS Rating Curve= 0 ,0
Exp/Cntr=0.3,0.1

Type RM Length L Ch R = 1 ,12000   ,500,500,500
BEGIN DESCRIPTION:
INKS 09 23.0
END DESCRIPTION:
XS GIS Cut Line= 4
      2896199.39     10157057.42      2896939.52     10157000.06
      2897082.53     10157033.84      2897598.14     10157293.06
#Sta/Elev= 30
  4110.7  1045.4    4140 1042.14  4260.6 1034.69  4337.7 1031.97  4498.2 1022.91
  4658.6 1020.22  4688.7 1016.32    4789 1018.02  4928.9 1018.07  4935.7  1015.6
  4941.6    1014  4951.9 1013.63  4971.2 1014.85  4976.3 1012.02  4997.1 1011.96
  4997.3 1011.46  5001.1 1011.96  5014.9    1012  5048.3 1015.68  5081.9 1023.94
    5147 1029.47  5316.3 1042.75  5344.2 1046.66  5427.9 1054.38  5484.8  1061.3
  5539.5 1064.67  5545.1  1066.8  5561.8  1065.9  5567.4 1067.31  5577.1 1067.23
#Mann= 7 ,-1 , 0
  4110.7     .05       0    4140     .12       0  4260.6     .05       0
  4935.7     .12       0  4997.1     .07       0  5001.1     .12       0
    5147     .05       0
Bank Sta=4997.1,5001.1
XS Rating Curve= 0 ,0
Exp/Cntr=0.3,0.1

Type RM Length L Ch R = 1 ,11500   ,500,500,500
BEGIN DESCRIPTION:
INKS 09 22.0
END DESCRIPTION:
XS GIS Cut Line= 3
      2896455.66     10157303.11      2896965.94     10157352.89
      2897355.66      10157453.1
#Sta/Elev= 30
  4487.3 1039.87  4540.7 1034.03  4617.9 1023.29  4644.6 1020.94  4678.2 1018.55
  4778.7 1017.89  4808.8 1016.56  4899.3 1015.85  4947.6 1014.58  4969.6 1012.59
  4995.4 1008.27  4995.6 1007.77  4999.4 1008.27  5023.3 1010.15  5030.7 1012.31
    5041 1013.45    5064 1018.99  5082.3 1021.66  5099.5 1023.58  5104.7 1022.88
  5141.4 1027.06  5186.2 1030.68  5247.5  1037.6  5262.5 1038.46    5298 1043.66
  5303.2 1043.35  5322.2 1046.77  5371.5 1053.35  5390.9 1056.77  5402.4 1058.74
#Mann= 7 ,-1 , 0
  4487.3     .12       0  4644.6     .05       0  4995.4     .03       0
  4999.4     .05       0  5141.4     .12       0  5322.2     .05       0
  5390.9     .12       0
Bank Sta=4995.4,4999.4
XS Rating Curve= 0 ,0
Exp/Cntr=0.3,0.1

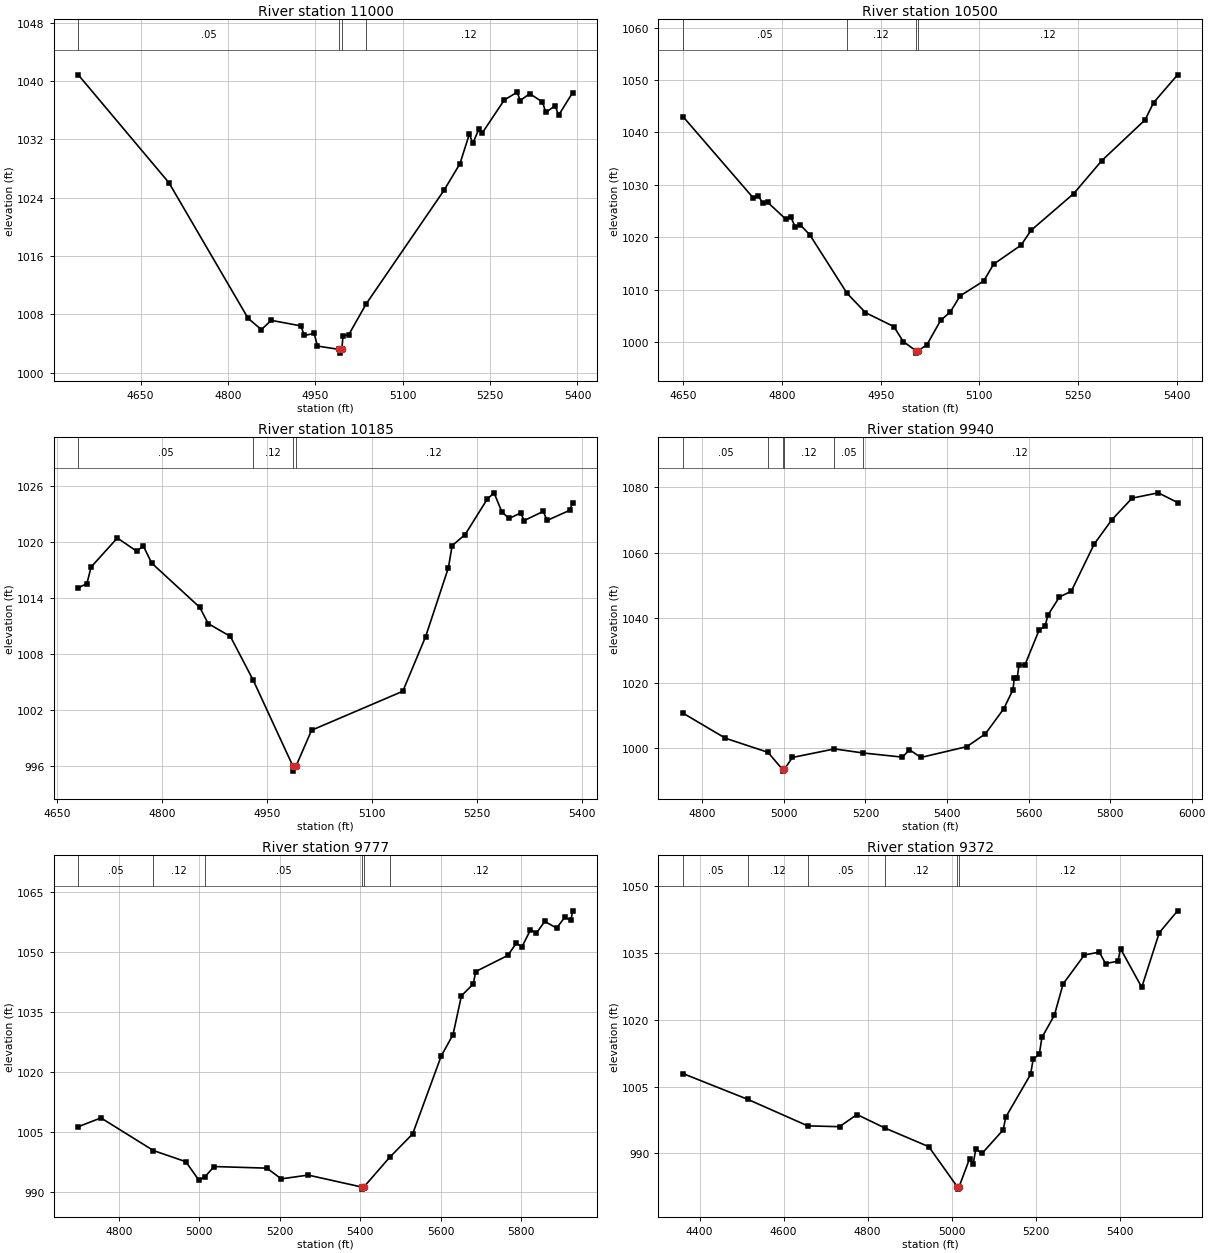
Type RM Length L Ch R = 1 ,11000   ,500,500,500
BEGIN DESCRIPTION:
INKS 09 21.0
END DESCRIPTION:
XS GIS Cut Line= 3
       2896755.7     10158253.09      2896952.86      10157840.7
      2897297.33     10157654.02
#Sta/Elev= 30
  4542.9 1040.83  4698.6 1026.04  4834.6 1007.45  4857.3 1005.92  4874.4 1007.18
  4925.3 1006.42  4930.9 1005.11    4948 1005.39  4953.6 1003.66  4991.4 1003.19
  4991.6 1002.69  4995.4 1003.19  4997.5 1005.09  5007.2 1005.19  5037.1 1009.42
  5170.7 1024.98  5198.3 1028.65  5214.5 1032.74  5220.2 1031.43  5230.7 1033.37
  5236.3 1032.83  5274.4 1037.38  5296.3 1038.44  5301.9 1037.31  5318.1 1038.25
    5340  1037.1  5345.7 1035.67  5361.9 1036.61  5367.5 1035.27  5391.8  1038.4
#Mann= 4 ,-1 , 0
  4542.9     .05       0  4991.4     .05       0  4995.4     .05       0
  5037.1     .12       0
Bank Sta=4991.4,4995.4
XS Rating Curve= 0 ,0
Exp/Cntr=0.3,0.1

Type RM Length L Ch R = 1 ,10500   ,315,315,315
BEGIN DESCRIPTION:
INKS 09 20.0
END DESCRIPTION:
XS GIS Cut Line= 3
      2897005.66     10158453.14      2897228.55     10158183.41
      2897455.71     10157853.08
#Sta/Elev= 30
  4650.1 1042.98  4756.3 1027.55  4764.1 1027.96  4770.6 1026.57  4778.5 1026.67
  4805.8 1023.49  4813.6 1023.87  4820.1 1022.03    4828 1022.37  4842.3  1020.5
  4898.9 1009.35    4927 1005.65    4970 1002.99  4984.3 1000.14  5003.1  998.43
  5003.4  997.93  5007.1  998.43    5020  999.47    5041 1004.15  5055.8 1005.78
  5070.7 1008.84  5106.6 1011.69  5121.5 1014.88  5163.4 1018.53  5178.3 1021.32
  5243.1 1028.33  5285.9 1034.63  5351.5 1042.39  5364.5 1045.68  5400.9 1050.98
#Mann= 4 ,-1 , 0
  4650.1     .05       0  4898.9     .12       0  5003.1     .07       0
  5007.1     .12       0
Bank Sta=5003.1,5007.1
XS Rating Curve= 0 ,0
Exp/Cntr=0.3,0.1

Type RM Length L Ch R = 1 ,10185   ,245,245,245
BEGIN DESCRIPTION:
INKS 09 19.0
END DESCRIPTION:
XS GIS Cut Line= 3
      2897301.55      10158673.9      2897455.68     10158403.11
       2897572.6     10158026.52
#Sta/Elev= 30
  4680.8 1015.09  4693.2 1015.55  4699.1 1017.32  4736.6 1020.43    4764 1019.03
  4773.8 1019.56  4785.6 1017.74  4854.3    1013  4866.3 1011.26    4898 1009.88
  4930.6 1005.19  4987.5  995.95  4987.8  995.45  4991.5  995.95  5013.9  999.83
  5144.2 1004.01  5176.8 1009.87  5209.3 1017.25  5214.6 1019.61  5233.2  1020.8
  5264.6 1024.58  5274.5 1025.27  5285.6 1023.22    5296 1022.52  5312.3 1023.11
  5317.5  1022.3  5344.8 1023.28  5350.1 1022.31  5382.6  1023.4  5386.7 1024.23
#Mann= 4 ,-1 , 0
  4680.8     .05       0  4930.6     .12       0  4987.5     .07       0
  4991.5     .12       0
Bank Sta=4987.5,4991.5
XS Rating Curve= 0 ,0
Exp/Cntr=0.3,0.1

Type RM Length L Ch R = 1 ,9940    ,163,163,163
BEGIN DESCRIPTION:
INKS 09 18.0
END DESCRIPTION:
XS GIS Cut Line= 4
      2897517.93     10158701.83      2897743.52     10158426.11
      2897943.67     10158013.56      2898256.62      10157767.8
#Sta/Elev= 30
  4752.8 1010.76  4856.4  1003.1  4960.8  998.78  4996.6  993.51  4996.8  993.01
  5000.6  993.51  5020.8   997.2  5123.9  999.82  5193.8  998.58  5290.8   997.3
  5307.8  999.57  5335.9   997.2  5448.8 1000.53  5493.9 1004.42  5539.1 1012.12
  5561.6 1017.94  5565.1 1021.42    5572 1021.42  5576.5 1025.52  5590.9 1025.54
  5626.2 1036.36  5640.6 1037.37    5647 1040.76  5675.9 1046.44  5704.8 1048.17
  5760.9 1062.62  5804.2 1070.08    5854 1076.73  5918.1 1078.36  5965.5 1075.39
#Mann= 6 ,-1 , 0
  4752.8     .05       0  4960.8     .12       0  4996.6     .07       0
  5000.6     .12       0  5123.9     .05       0  5193.8     .12       0
Bank Sta=4996.6,5000.6
XS Rating Curve= 0 ,0
Exp/Cntr=0.3,0.1

Type RM Length L Ch R = 1 ,9777    ,405,405,405
BEGIN DESCRIPTION:
Mapping XS 003c3219
END DESCRIPTION:
XS GIS Cut Line= 6
      2897600.52      10158747.2      2897810.15     10158607.88
      2897859.63     10158476.37       2897837.5     10158394.34
      2898021.09     10158106.58      2898354.44     10157865.68
#Sta/Elev= 30
  4698.9 1006.38  4755.3 1008.58  4885.9 1000.44  4966.4  997.67  4998.4  993.13
  5013.9  993.88  5036.6  996.46    5168  996.06  5203.9  993.39  5270.7  994.33
    5405  991.33  5405.2  990.83    5409  991.33  5473.6  998.77  5530.6 1004.57
  5601.7    1024  5631.1 1029.33    5652 1039.01  5681.4 1041.95  5687.6 1045.06
  5767.3 1049.07  5788.2 1052.08  5802.9 1051.28  5823.7 1055.42  5838.4 1054.62
  5859.3 1057.56  5888.7 1055.88  5909.6 1058.64  5924.3 1057.79  5928.7 1060.19
#Mann= 6 ,-1 , 0
  4698.9     .05       0  4885.9     .12       0  5013.9     .05       0
    5405     .07       0    5409     .05       0  5473.6     .12       0
Bank Sta=5405,5409
XS Rating Curve= 0 ,0
Exp/Cntr=0.3,0.1

Type RM Length L Ch R = 1 ,9372    ,358,358,358
BEGIN DESCRIPTION:
Mapping XS 4ebf2ac1
END DESCRIPTION:
XS GIS Cut Line= 5
      2897695.55     10158731.59      2897883.07     10158607.88
      2898035.41     10158425.59      2898048.43     10158204.23
      2898451.37     10157919.58
#Sta/Elev= 30
  4360.7  1007.9    4515 1002.11  4657.2  996.18    4733  995.99  4774.6  998.72
  4841.1  995.69  4945.6   991.5  5013.7  982.47    5014  981.97  5017.7  982.47
  5042.7  988.81  5051.3  987.56  5057.5  990.99  5072.2  989.97  5122.7  995.26
  5128.9  998.14    5188 1007.73  5194.1 1011.13  5208.9 1012.32    5215 1016.03
  5244.6 1021.01  5265.5 1028.05    5316 1034.54  5351.7 1035.19  5366.5 1032.61
  5396.1 1033.16  5402.2 1035.94  5452.7 1027.29  5494.5 1039.55    5538 1044.46
#Mann= 6 ,-1 , 0
  4360.7     .05       0    4515     .12       0  4657.2     .05       0
  4841.1     .12       0  5013.7     .07       0  5017.7     .12       0
Bank Sta=5013.7,5017.7
XS Rating Curve= 0 ,0
Exp/Cntr=0.3,0.1