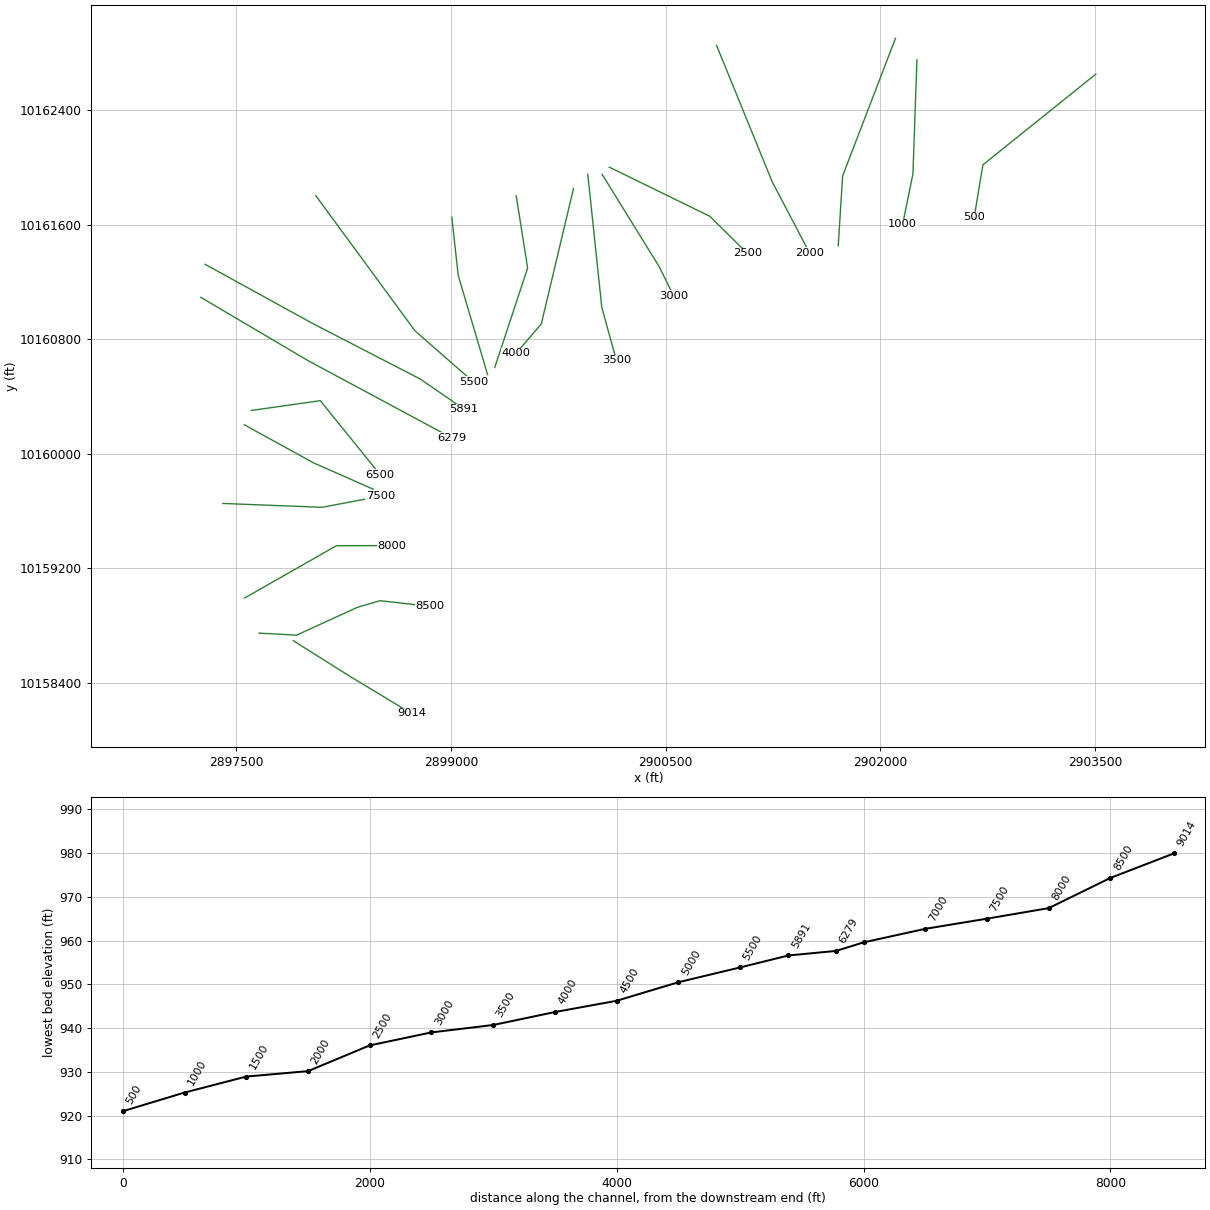
HEC-RAS study INKS 09.prj: INKS 09 Base Level Engineering

--- INKS 09.g01 (geometry) --- (continued)

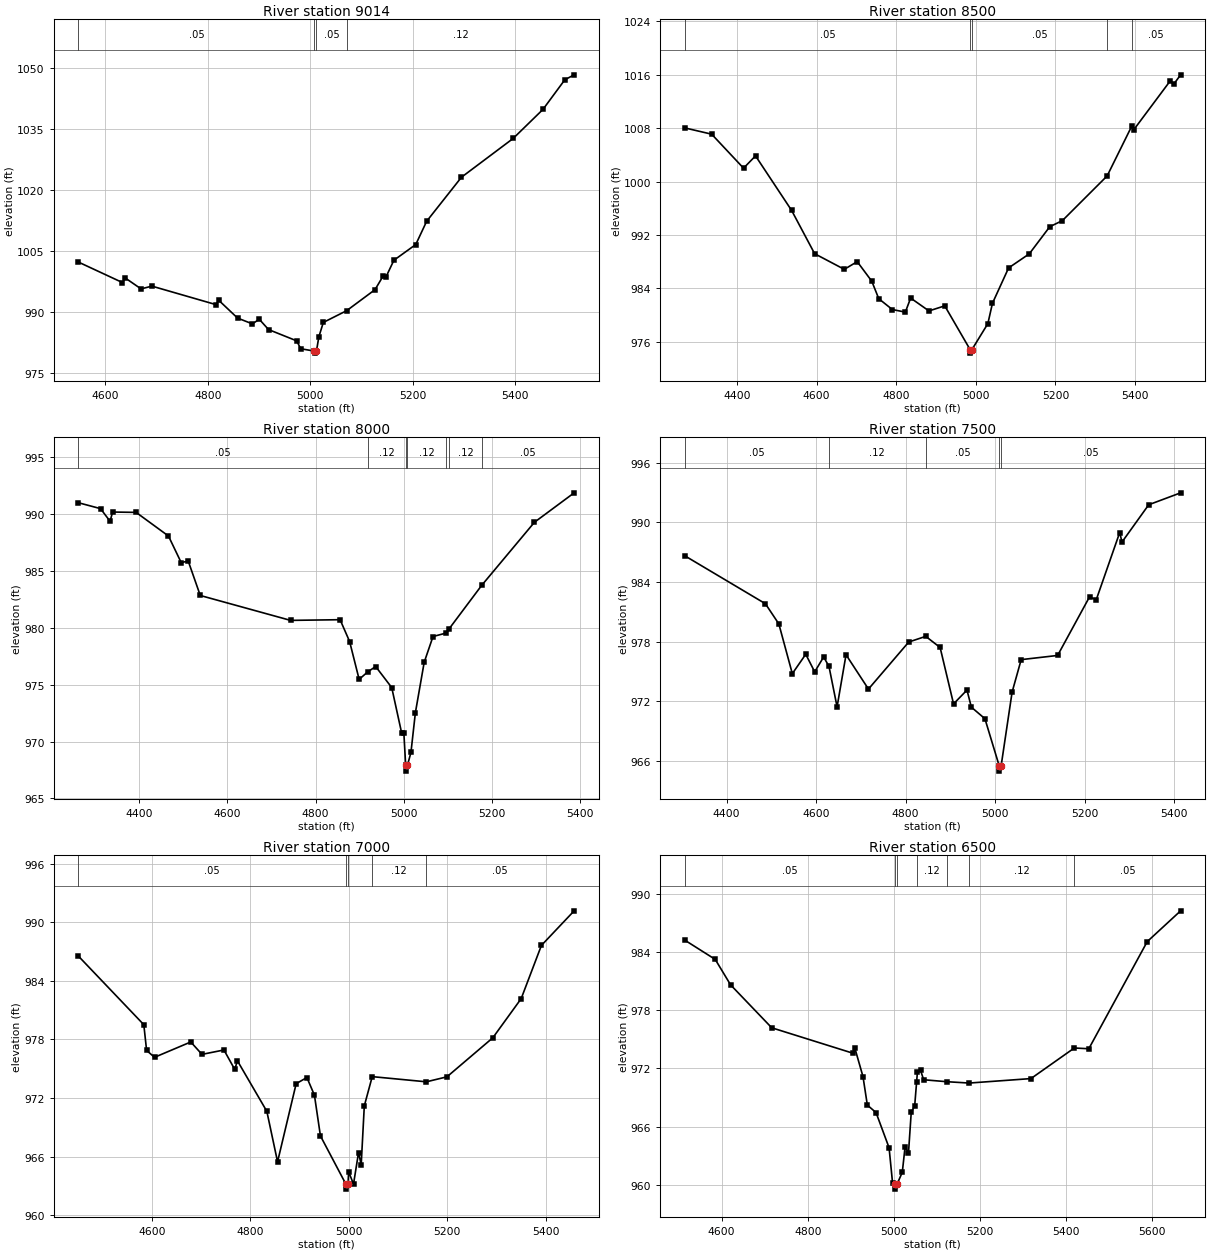
Type RM Length L Ch R = 1 ,9014    ,514,514,514
BEGIN DESCRIPTION:
Mapping XS 7cb39b70
END DESCRIPTION:
XS GIS Cut Line= 4
      2897898.02     10158694.04      2898213.92     10158495.21
      2898311.11     10158434.72      2898722.38     10158186.33
#Sta/Elev= 30
    4547 1002.32    4633  997.28  4638.9  998.37  4669.5  995.71  4690.7  996.39
  4815.5  991.85  4821.4  992.88  4857.9  988.53  4886.9   987.1  4900.3  988.24
  4918.4   985.7  4973.4  982.92  4981.2  980.98    5008   980.4  5008.3   979.9
    5012   980.4  5016.6  983.88  5025.4  987.46    5071  990.35  5126.3  995.52
  5141.8   998.8  5147.7  998.64  5163.2 1002.76  5205.9 1006.63  5227.2 1012.36
  5295.1 1023.19    5396 1032.73  5454.3 1039.89    5497 1047.19  5515.2  1048.4
#Mann= 4 ,-1 , 0
    4547     .05       0    5008     .05       0    5012     .05       0
    5071     .12       0
Bank Sta=5008,5012
XS Rating Curve= 0 ,0
Exp/Cntr=0.3,0.1

Type RM Length L Ch R = 1 ,8500    ,500,500,500
BEGIN DESCRIPTION:
INKS 09 17.0
END DESCRIPTION:
XS GIS Cut Line= 5
      2897658.27     10158746.97      2897920.85      10158732.9
      2898346.71     10158927.55      2898504.72     10158973.66
      2898852.41     10158934.39
#Sta/Elev= 30
  4268.8 1008.03  4336.3 1007.09  4416.4    1002  4446.5 1003.84  4537.2  995.67
    4595  989.19  4669.5  986.85    4702     988  4738.6  985.07  4756.1  982.45
  4790.2  980.83  4822.9  980.44  4836.2  982.55  4882.2  980.62  4921.9  981.38
  4985.9   974.8  4986.1   974.3  4989.9   974.8  5030.2  978.72  5041.7  981.76
  5082.3  987.06  5134.3  989.17  5185.7  993.23  5217.5  994.15  5329.9 1000.84
  5391.6 1008.28  5397.1 1007.78  5487.6 1015.01  5497.7 1014.62  5514.5 1015.98
#Mann= 5 ,-1 , 0
  4268.8     .05       0  4985.9     .05       0  4989.9     .05       0
  5329.9     .12       0  5391.6     .05       0
Bank Sta=4985.9,4989.9
XS Rating Curve= 0 ,0
Exp/Cntr=0.3,0.1

Type RM Length L Ch R = 1 ,8000    ,500,500,500
BEGIN DESCRIPTION:
INKS 09 16.0
END DESCRIPTION:
XS GIS Cut Line= 3
      2897558.04     10158992.64      2898199.59     10159357.82
      2898585.79     10159358.62
#Sta/Elev= 30
  4261.8  991.01  4312.1  990.49  4333.7  989.38  4339.6  990.19  4392.8  990.16
  4466.2  988.08  4495.1  985.74    4511  985.88  4538.3  982.85    4743  980.66
  4855.4  980.72    4877   978.8  4898.6  975.47  4917.7  976.12  4936.1   976.6
  4972.5  974.75  4994.9  970.77    5000  970.77  5004.1   967.9  5004.3   967.4
  5008.1   967.9  5016.1  969.05  5026.1  972.53  5046.1  976.97  5066.1  979.24
  5096.3  979.55  5102.9  979.93  5176.5  983.74  5296.1  989.29  5386.2  991.88
#Mann= 7 ,-1 , 0
  4261.8     .05       0  4917.7     .12       0  5004.1     .07       0
  5008.1     .12       0  5096.3     .05       0  5102.9     .12       0
  5176.5     .05       0
Bank Sta=5004.1,5008.1
XS Rating Curve= 0 ,0
Exp/Cntr=0.3,0.1

Type RM Length L Ch R = 1 ,7500    ,500,500,500
BEGIN DESCRIPTION:
INKS 09 15.0
END DESCRIPTION:
XS GIS Cut Line= 3
      2897405.71     10159653.11      2898098.49     10159626.24
       2898505.7     10159703.11
#Sta/Elev= 30
  4306.7  986.64  4486.8  981.82  4516.8  979.79  4546.9  974.79  4576.9  976.74
  4596.9  974.97  4616.9  976.47  4628.8  975.52  4646.9  971.45  4666.9  976.69
    4717  973.24    4807  977.97    4845  978.54  4877.1  977.42  4907.1  971.75
  4937.1  973.14  4946.9  971.42  4977.2  970.26  5009.3  965.49  5009.5  964.99
  5013.3  965.49  5037.9  972.93  5058.2   976.2  5139.6  976.62  5210.9  982.51
  5225.9  982.22  5278.3  988.98  5283.4  988.02  5343.1  991.77  5414.4  992.97
#Mann= 5 ,-1 , 0
  4306.7     .05       0  4628.8     .12       0    4845     .05       0
  5009.3     .05       0  5013.3     .05       0
Bank Sta=5009.3,5013.3
XS Rating Curve= 0 ,0
Exp/Cntr=0.3,0.1

Type RM Length L Ch R = 1 ,7000    ,500,500,500
BEGIN DESCRIPTION:
INKS 09 14.0
END DESCRIPTION:
XS GIS Cut Line= 3
      2897555.67     10160203.12      2898036.59     10159938.11
      2898455.67     10159753.12
#Sta/Elev= 30
  4450.9  986.54  4583.9  979.51  4589.6  976.87  4605.7  976.17  4679.3  977.74
  4702.1  976.47  4746.7  976.92  4768.5  974.94  4774.2   975.8  4833.8  970.64
  4855.6  965.47  4893.4  973.47  4915.2   974.1  4930.5  972.29  4942.7  968.12
  4994.5  963.17  4994.8  962.67  4998.7  963.17    5000  964.45  5009.9  963.18
  5020.1  966.42  5025.5  965.17  5031.8  971.19  5047.9  974.19  5157.9  973.66
  5199.7  974.17  5292.9  978.17  5350.5  982.18  5391.6  987.63  5458.1  991.17
#Mann= 5 ,-1 , 0
  4450.9     .05       0  4994.5     .05       0  4998.7     .05       0
  5047.9     .12       0  5157.9     .05       0
Bank Sta=4994.5,4998.7
XS Rating Curve= 0 ,0
Exp/Cntr=0.3,0.1

Type RM Length L Ch R = 1 ,6500    ,221,221,221
BEGIN DESCRIPTION:
INKS 09 13.0
END DESCRIPTION:
XS GIS Cut Line= 3
       2897605.7     10160303.11      2898086.59     10160371.37
      2898505.68     10159853.12
#Sta/Elev= 30
  4514.3   985.2    4585  983.22  4620.7   980.6  4716.3  976.18  4904.4  973.57
  4909.5  974.08  4928.4  971.15  4938.5  968.22  4958.7  967.45    4989  963.83
    4997  960.25  5003.3  960.07  5003.5  959.57  5007.5  960.07  5019.7  961.31
  5026.2  963.92  5034.1   963.3  5040.5  967.48  5048.5  968.14  5052.9  970.55
  5054.9  971.65  5062.1  971.81  5069.3  970.83  5122.8  970.63  5175.1  970.49
  5318.7  970.95  5419.5   974.1  5453.1  974.02  5588.9  985.05  5666.5  988.22
#Mann= 7 ,-1 , 0
  4514.3     .05       0  5003.3     .05       0  5007.5     .05       0
  5052.9     .12       0  5122.8     .05       0  5175.1     .12       0
  5419.5     .05       0
Bank Sta=5003.3,5007.5
XS Rating Curve= 0 ,0
Exp/Cntr=0.3,0.1

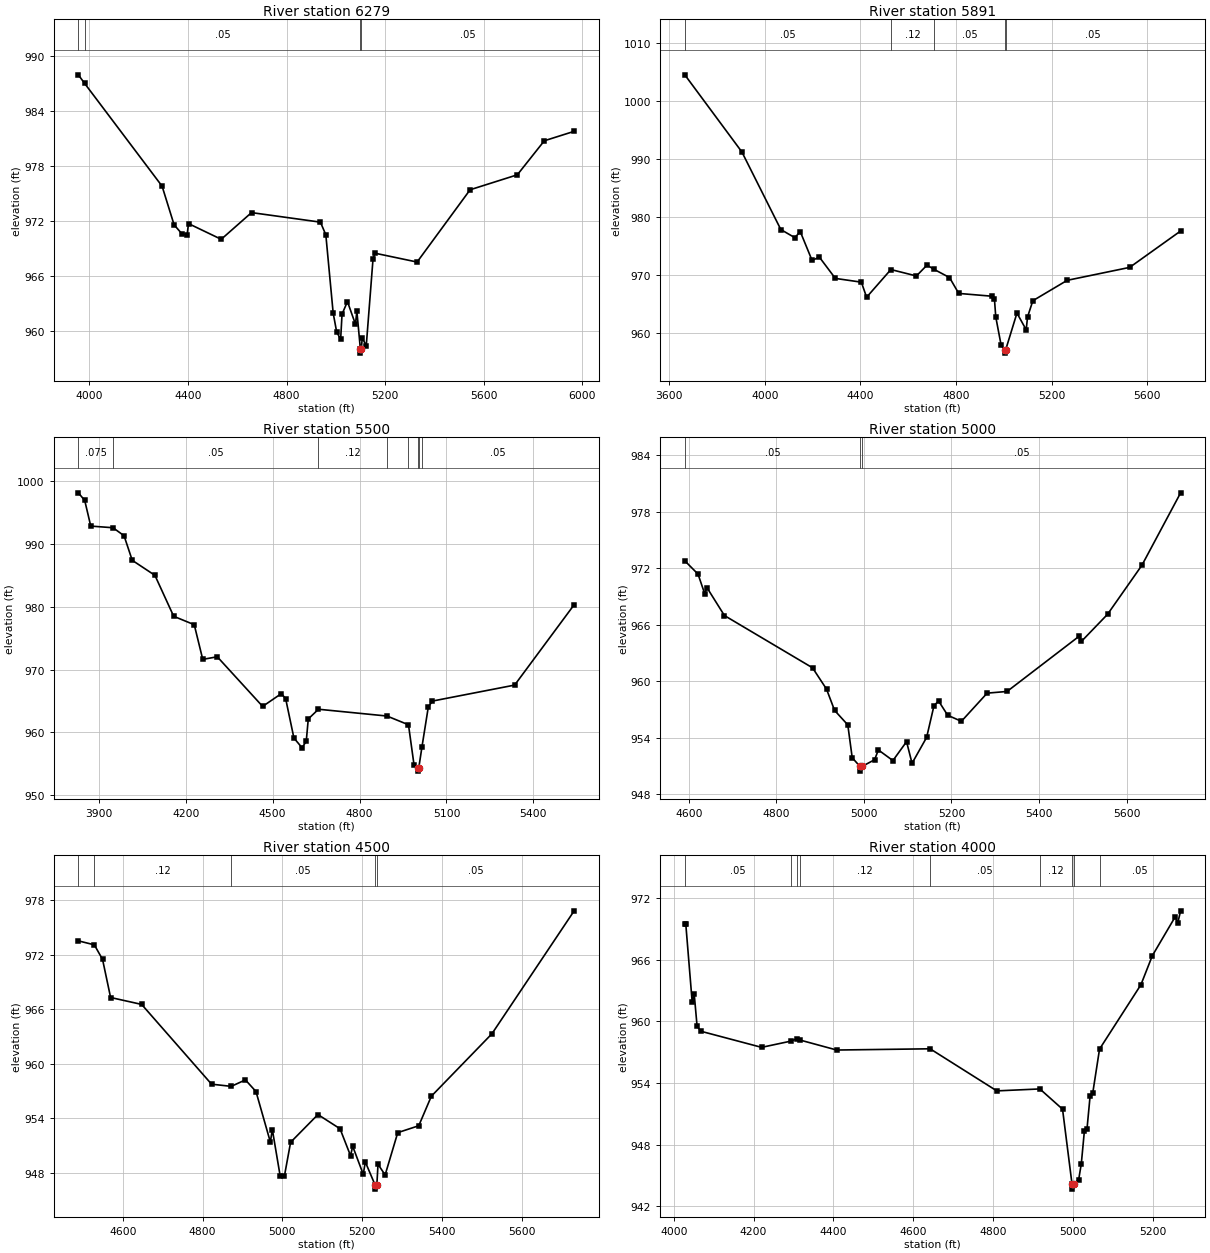
Type RM Length L Ch R = 1 ,6279    ,388,388,388
BEGIN DESCRIPTION:
Mapping XS d749ff6e
END DESCRIPTION:
XS GIS Cut Line= 3
      2897252.18      10161093.3      2897999.21      10160652.1
      2899006.96     10160110.62
#Sta/Elev= 30
  3955.1  987.97  3980.2  987.05  4294.9  975.83  4343.6  971.62  4374.9  970.65
  4396.3   970.5  4402.1  971.75  4534.8  970.04  4657.7  972.95  4937.3  971.91
  4959.2  970.53    4989     962  5003.1  959.95  5019.3  959.13    5025  961.88
  5046.9  963.25  5079.4  960.78  5085.1  962.21  5099.2  958.13  5099.4  957.63
  5103.4  958.13    5107   959.3  5123.2  958.42  5150.8  967.94  5159.3  968.52
  5329.5  967.56  5544.5  975.44  5736.1  977.07  5845.6  980.78  5966.7  981.81
#Mann= 4 ,-1 , 0
  3955.1    .075       0  3980.2     .05       0  5099.2     .03       0
  5103.4     .05       0
Bank Sta=5099.2,5103.4
XS Rating Curve= 0 ,0
Exp/Cntr=0.3,0.1

Type RM Length L Ch R = 1 ,5891    ,391,391,391
BEGIN DESCRIPTION:
Mapping XS d77bcacd
END DESCRIPTION:
XS GIS Cut Line= 4
      2897282.29      10161323.9      2898029.29      10160912.8
      2898786.33     10160521.75      2899091.39     10160311.71
#Sta/Elev= 30
  3664.8 1004.59  3903.8  991.28  4066.7   977.9  4125.2   976.5  4148.1  977.54
  4197.4  972.58    4228  973.14  4294.9  969.47  4403.8  968.82  4425.6  966.22
  4527.3     971  4634.1  969.89  4678.4  971.76  4708.6  971.02  4772.6  969.62
  4811.3  966.88  4952.4  966.39  4960.7  965.91  4966.3  962.81  4988.5  957.99
  5002.9  957.08  5003.2  956.58  5007.2  957.08  5054.9  963.49  5093.6   960.6
  5099.2  962.81  5121.4  965.62  5265.2  969.14  5526.6  971.37  5739.9  977.65
#Mann= 5 ,-1 , 0
  3664.8     .05       0  4527.3     .12       0  4708.6     .05       0
  5002.9     .05       0  5007.2     .05       0
Bank Sta=5002.9,5007.2
XS Rating Curve= 0 ,0
Exp/Cntr=0.3,0.1

Type RM Length L Ch R = 1 ,5500    ,500,500,500
BEGIN DESCRIPTION:
INKS 09 11.0
END DESCRIPTION:
XS GIS Cut Line= 3
      2898055.66     10161803.14      2898748.49     10160859.21
      2899155.66     10160503.14
#Sta/Elev= 30
  3829.1   998.1  3851.1   996.9    3872  992.81  3948.8  992.55  3986.9  991.28
  4015.2  987.37  4093.5  984.98  4158.3  978.47  4229.3  977.13  4258.6  971.62
  4308.8  972.03  4465.4  964.14  4530.2  966.18  4544.9  965.36  4573.4  959.11
  4601.3  957.58  4615.9  958.57    4623  962.15  4658.2  963.69  4894.7  962.61
  4968.9  961.22  4987.9   954.9  5000.1  954.35  5000.4  953.85  5004.4  954.35
  5015.6  957.75  5037.4  964.06  5051.6  964.99  5335.4  967.53  5540.9  980.31
#Mann= 8 ,-1 , 0
  3829.1    .075       0  3948.8     .05       0  4658.2     .12       0
  4894.7     .05       0  4968.9     .12       0  5000.1     .07       0
  5004.4     .12       0  5015.6     .05       0
Bank Sta=5000.1,5004.4
XS Rating Curve= 0 ,0
Exp/Cntr=0.3,0.1

Type RM Length L Ch R = 1 ,5000    ,500,500,500
BEGIN DESCRIPTION:
INKS 09 10.0
END DESCRIPTION:
XS GIS Cut Line= 3
      2899005.69      10161653.1      2899050.37     10161246.55
      2899255.69      10160553.1
#Sta/Elev= 30
    4591   972.8  4621.2  971.39  4636.5   969.3  4641.5  969.96  4681.5  966.99
  4882.7  961.44  4914.6  959.18    4933  956.92  4963.2  955.38  4973.3  951.89
    4991  950.97  4991.3  950.47  4995.8  950.97  5024.4  951.68    5033  952.72
  5066.2  951.59  5097.4   953.6  5109.9   951.3  5143.2  954.05    5160  957.42
  5170.5  957.92  5191.3   956.4  5222.6  955.76  5281.4  958.75  5326.9  958.93
  5491.4  964.79  5496.6  964.24  5556.3  967.12  5634.8  972.33  5723.2  980.02
#Mann= 3 ,-1 , 0
    4591     .05       0    4991     .03       0  4995.8     .05       0
Bank Sta=4991,4995.8
XS Rating Curve= 0 ,0
Exp/Cntr=0.3,0.1

Type RM Length L Ch R = 1 ,4500    ,500,500,500
BEGIN DESCRIPTION:
INKS 09 9.0
END DESCRIPTION:
XS GIS Cut Line= 3
      2899455.69     10161803.07      2899535.27     10161297.91
       2899305.7     10160603.15
#Sta/Elev= 30
  4488.6  973.53  4528.7  973.09  4549.3  971.49  4569.5   967.3  4647.3  966.54
  4822.6  957.77  4871.9  957.53  4907.5  958.24    4934  956.96    4970  951.41
    4975  952.78  4994.7  947.66  5005.2  947.65  5020.8  951.38  5089.3  954.43
  5144.7  952.87  5171.1   949.9  5176.4  950.95  5202.9  947.86  5208.1  949.22
  5232.2  946.73  5232.5  946.23  5237.1  946.73  5239.9  948.96  5257.8  947.79
  5289.4  952.44  5342.1   953.2  5373.7  956.45  5525.5  963.31  5731.7  976.83
#Mann= 5 ,-1 , 0
  4488.6     .05       0  4528.7     .12       0  4871.9     .05       0
  5232.2     .05       0  5237.1     .05       0
Bank Sta=5232.2,5237.1
XS Rating Curve= 0 ,0
Exp/Cntr=0.3,0.1

Type RM Length L Ch R = 1 ,4000    ,500,500,500
BEGIN DESCRIPTION:
INKS 09 8.0
END DESCRIPTION:
XS GIS Cut Line= 3
      2899855.67     10161853.07      2899630.85     10160907.22
      2899455.66     10160703.09
#Sta/Elev= 30
  4027.8  969.47  4030.3  969.47  4046.3  961.87  4051.4  962.65  4058.6  959.51
  4068.9  959.03  4220.1  957.47  4293.6  958.08  4308.8  958.32  4316.4  958.18
  4408.1  957.21  4641.9  957.33  4808.9  953.23  4916.6  953.42  4973.4  951.45
  4997.1  944.16  4997.4  943.66    5002  944.16  5013.8  944.59  5020.4  946.14
  5028.1  949.33  5034.7  949.55  5042.3  952.69  5048.9  952.99    5066   957.3
  5169.6  963.57  5198.2   966.4  5255.2  970.17  5261.8   969.6    5269  970.77
#Mann= 9 ,-1 , 0
  4027.8     .05       0  4293.6     .12       0  4308.8     .05       0
  4316.4     .12       0  4641.9     .05       0  4916.6     .12       0
  4997.1     .07       0    5002     .12       0    5066     .05       0
Bank Sta=4997.1,5002
XS Rating Curve= 0 ,0
Exp/Cntr=0.3,0.1

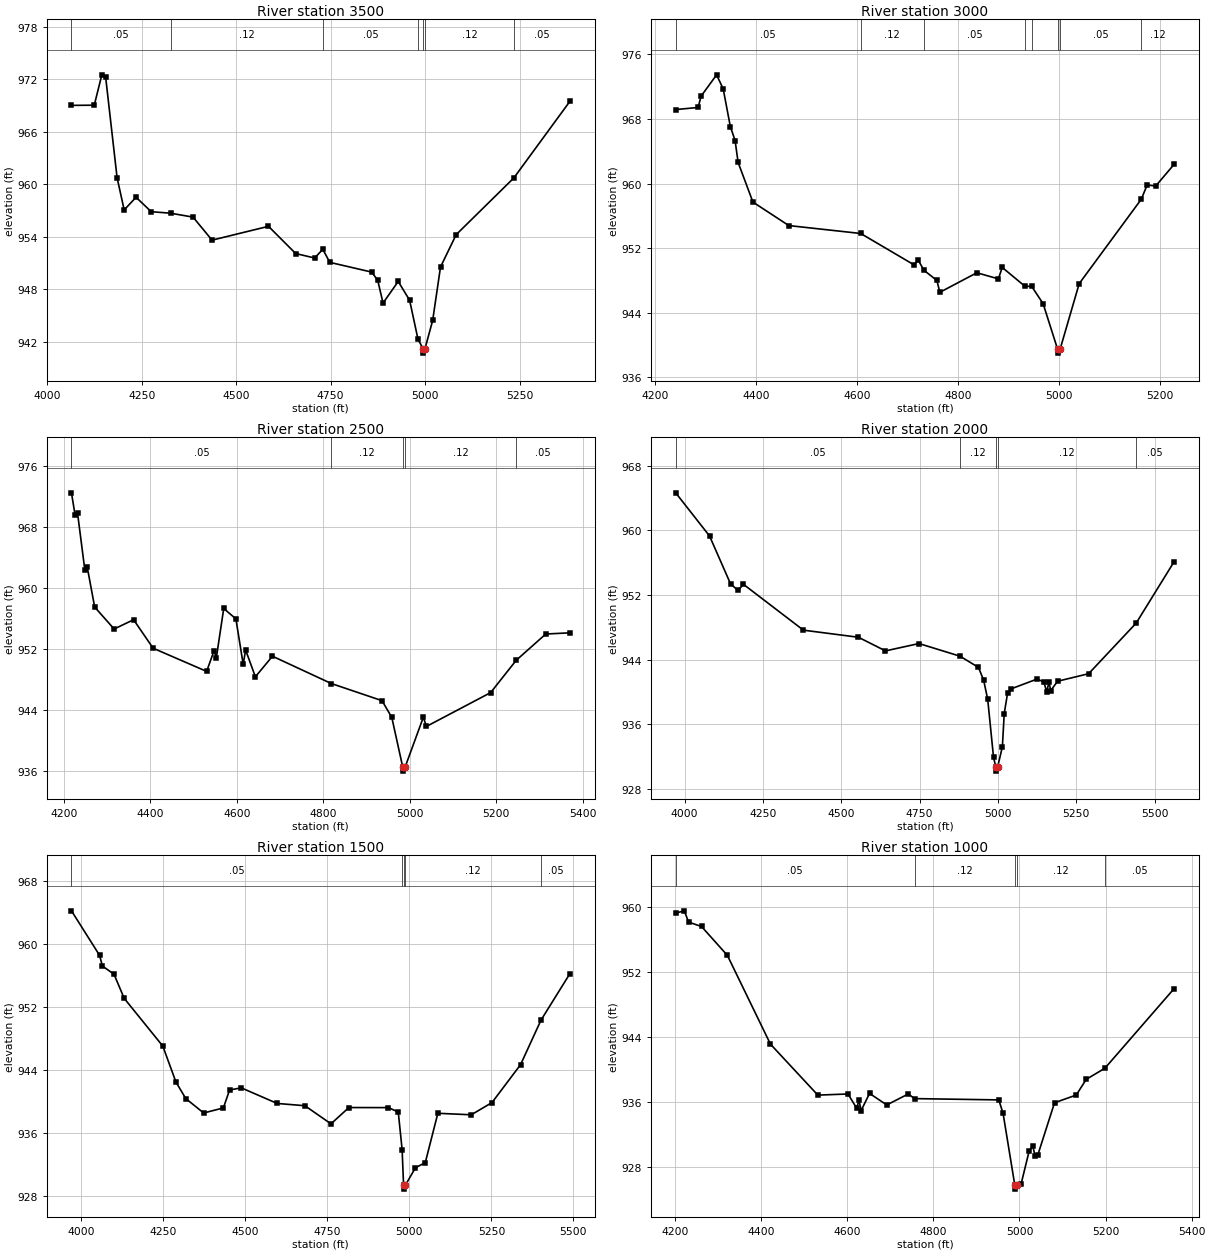
Type RM Length L Ch R = 1 ,3500    ,500,500,500
BEGIN DESCRIPTION:
INKS 09 7.0
END DESCRIPTION:
XS GIS Cut Line= 3
      2899955.69      10161953.1       2900053.7     10161022.55
       2900155.7     10160653.07
#Sta/Elev= 30
  4064.3  969.01  4124.6  969.03  4144.7   972.5  4154.8  972.23    4185  960.75
  4203.8  957.06  4235.2  958.51  4275.4  956.86  4326.5  956.69  4386.1  956.24
  4436.3  953.61  4585.7  955.19  4657.6  952.08  4707.8  951.57  4729.4  952.56
    4748  951.07  4858.7  949.96  4874.7  949.03  4888.8  946.42    4929  948.89
  4959.2  946.74  4981.2  942.31  4994.7   941.2  4995.1   940.7  4999.8   941.2
  5020.2  944.44  5040.9  950.54  5082.4  954.24    5235  960.72  5383.3  969.47
#Mann= 7 ,-1 , 0
  4064.3     .05       0  4326.5     .12       0  4729.4     .05       0
  4981.2     .12       0  4994.7     .07       0  4999.8     .12       0
    5235     .05       0
Bank Sta=4994.7,4999.8
XS Rating Curve= 0 ,0
Exp/Cntr=0.3,0.1

Type RM Length L Ch R = 1 ,3000    ,500,500,500
BEGIN DESCRIPTION:
INKS 09 6.0
END DESCRIPTION:
XS GIS Cut Line= 3
      2900055.67     10161953.14      2900454.85     10161307.35
       2900555.7     10161103.09
#Sta/Elev= 30
  4240.8  969.16  4285.2  969.42  4291.1  970.82  4321.8  973.46  4334.9  971.71
    4349  967.06  4358.4  965.33  4364.4  962.62  4393.7  957.71  4464.8   954.8
  4607.2  953.82  4711.9  949.97  4721.4  950.48  4732.5  949.26    4758  948.01
  4763.9  946.54  4837.2  948.96  4879.8   948.2  4887.4  949.62  4932.3  947.29
  4945.8  947.27  4968.4  945.13    4997  939.51  4997.4  939.01  5002.1  939.51
  5039.8  947.61  5162.9  958.07  5174.4  959.83  5191.3  959.69  5227.8  962.38
#Mann= 8 ,-1 , 0
  4240.8     .05       0  4607.2     .12       0  4732.5     .05       0
  4932.3     .12       0  4945.8     .05       0    4997     .05       0
  5002.1     .05       0  5162.9     .12       0
Bank Sta=4997,5002.1
XS Rating Curve= 0 ,0
Exp/Cntr=0.3,0.1

Type RM Length L Ch R = 1 ,2500    ,500,500,500
BEGIN DESCRIPTION:
INKS 09 5.0
END DESCRIPTION:
XS GIS Cut Line= 3
      2900105.64     10162003.13      2900808.25     10161659.82
      2901071.56     10161400.02
#Sta/Elev= 30
    4218  972.54  4226.5  969.57  4232.1  969.86    4249  962.37  4254.6  962.76
  4271.6  957.56  4316.6  954.68  4361.6   955.9  4406.7  952.16  4530.4  949.12
  4547.4  951.81  4552.9  950.93  4569.9  957.37    4598  956.01  4614.9  950.04
  4620.5  951.93    4643  948.41  4682.5  951.11  4818.5  947.53  4935.7  945.28
  4958.3  943.09  4983.7  936.54  4984.1  936.04  4988.9  936.54  5031.2  943.11
  5038.3   941.9  5186.8  946.34  5245.9  950.58  5314.1  954.02  5369.9  954.18
#Mann= 5 ,-1 , 0
    4218     .05       0  4818.5     .12       0  4983.7     .07       0
  4988.9     .12       0  5245.9     .05       0
Bank Sta=4983.7,4988.9
XS Rating Curve= 0 ,0
Exp/Cntr=0.3,0.1

Type RM Length L Ch R = 1 ,2000    ,500,500,500
BEGIN DESCRIPTION:
INKS 09 4.0
END DESCRIPTION:
XS GIS Cut Line= 3
       2900855.7     10162853.08      2901244.35     10161900.62
       2901505.7     10161403.09
#Sta/Elev= 30
  3971.3  964.67  4079.3  959.32  4146.4  953.38  4170.4  952.56  4187.3  953.33
  4378.9  947.64  4554.5  946.76  4640.8  945.07  4747.8  945.98  4878.9  944.41
  4937.6  943.02  4954.1  941.44  4967.1  939.06  4985.7  931.86  4993.2  930.66
  4993.7  930.16  4998.7  930.66  5013.9  933.18  5019.8   937.3  5030.3  939.79
  5042.4  940.37  5124.1  941.57  5146.2  941.23  5155.3     940  5162.6  941.18
  5168.2  940.15  5190.3  941.31  5289.2  942.24    5441  948.52    5562  956.13
#Mann= 5 ,-1 , 0
  3971.3     .05       0  4878.9     .12       0  4993.2     .07       0
  4998.7     .12       0    5441     .05       0
Bank Sta=4993.2,4998.7
XS Rating Curve= 0 ,0
Exp/Cntr=0.3,0.1

Type RM Length L Ch R = 1 ,1500    ,500,500,500
BEGIN DESCRIPTION:
INKS 09 3.0
END DESCRIPTION:
XS GIS Cut Line= 3
      2902105.68     10162903.09      2901736.32     10161941.49
      2901705.69     10161453.15
#Sta/Elev= 30
  3969.9  964.26  4055.6  958.61  4064.2  957.25  4099.6  956.21  4130.6  953.15
  4248.4  947.08  4288.2  942.54  4318.3  940.42  4372.9  938.59    4433  939.23
  4451.9  941.51  4487.6  941.78    4597   939.8  4681.6  939.51    4761  937.21
  4815.6  939.28  4935.7  939.27  4966.1  938.72  4977.9  933.92  4982.3  929.42
  4982.7  928.92  4987.8  929.42  5018.4  931.63  5048.5  932.29  5086.8  938.55
  5188.7  938.36  5251.8  939.91    5339  944.73  5401.1  950.37  5489.3  956.28
#Mann= 5 ,-1 , 0
  3969.9     .05       0  4977.9     .12       0  4982.3     .07       0
  4987.8     .12       0  5401.1     .05       0
Bank Sta=4982.3,4987.8
XS Rating Curve= 0 ,0
Exp/Cntr=0.3,0.1

Type RM Length L Ch R = 1 ,1000    ,500,500,500
BEGIN DESCRIPTION:
INKS 09 2.0
END DESCRIPTION:
XS GIS Cut Line= 3
      2902255.68     10162753.12      2902227.59     10161955.11
      2902155.68     10161603.08
#Sta/Elev= 30
  4201.5  959.27  4221.5  959.55  4231.5  958.16  4261.5  957.62  4321.6  954.06
  4421.6  943.13  4531.7  936.85  4601.8  936.99  4621.8  935.24  4627.3   936.2
  4632.3  934.95  4651.8  937.06  4691.8  935.64  4741.8  936.99  4756.4  936.42
    4952  936.26    4962   934.6  4989.2  925.77  4989.6  925.27  4994.8  925.77
  5003.6  925.85  5022.5  929.95    5031   930.6  5036.1   929.4  5042.9  929.51
  5081.5  935.91    5132  936.86  5155.1  938.79  5198.5  940.16  5359.3  949.97
#Mann= 5 ,-1 , 0
  4201.5     .05       0  4756.4     .12       0  4989.2     .07       0
  4994.8     .12       0  5198.5     .05       0
Bank Sta=4989.2,4994.8
XS Rating Curve= 0 ,0
Exp/Cntr=0.3,0.1

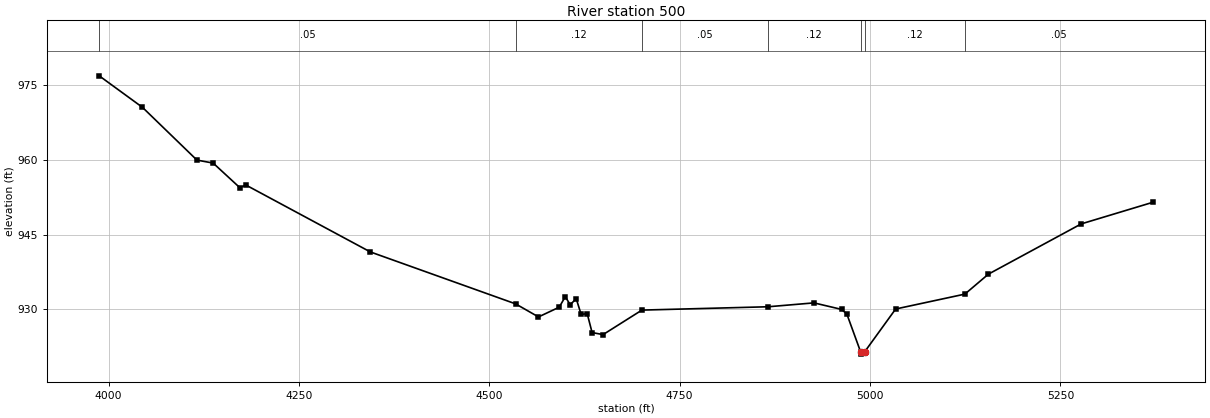
Type RM Length L Ch R = 1 ,500     ,0,0,0
BEGIN DESCRIPTION:
INKS 09 1.0
END DESCRIPTION:
XS GIS Cut Line= 3
      2903505.68     10162653.11      2902716.51     10162019.27
      2902655.68     10161653.09
#Sta/Elev= 30
  3987.8  976.88  4044.6  970.55  4116.1  959.96  4137.4  959.36  4172.6   954.4
  4180.2  954.97  4343.8  941.52  4534.6  931.09  4564.6  928.47  4591.8  930.42
  4599.8  932.53  4606.2  930.93  4614.2  932.12  4620.6  928.98  4628.6  929.12
    4635  925.33  4649.4  924.92  4700.4  929.84  4866.1  930.51  4926.3  931.29
  4962.6  929.98  4969.5  929.06  4987.5   921.5  4987.9     921  4993.1   921.5
  5033.6  930.06  5124.5  933.05  5155.4  937.06  5277.3  947.15  5371.2  951.48
#Mann= 7 ,-1 , 0
  3987.8     .05       0  4534.6     .12       0  4700.4     .05       0
  4866.1     .12       0  4987.5     .07       0  4993.1     .12       0
  5124.5     .05       0
Bank Sta=4987.5,4993.1
XS Rating Curve= 0 ,0
Exp/Cntr=0.3,0.1
Stream Node=INKS 09         ,Reach-1         , 0 , 0 ,Upstream end
Stream Node=INKS 09         ,Reach-1         , 0 , 1 ,Downstream end

Chan Stop Cuts=-1
Use User Specified Reach Order=0
Composite Channel Slope=5