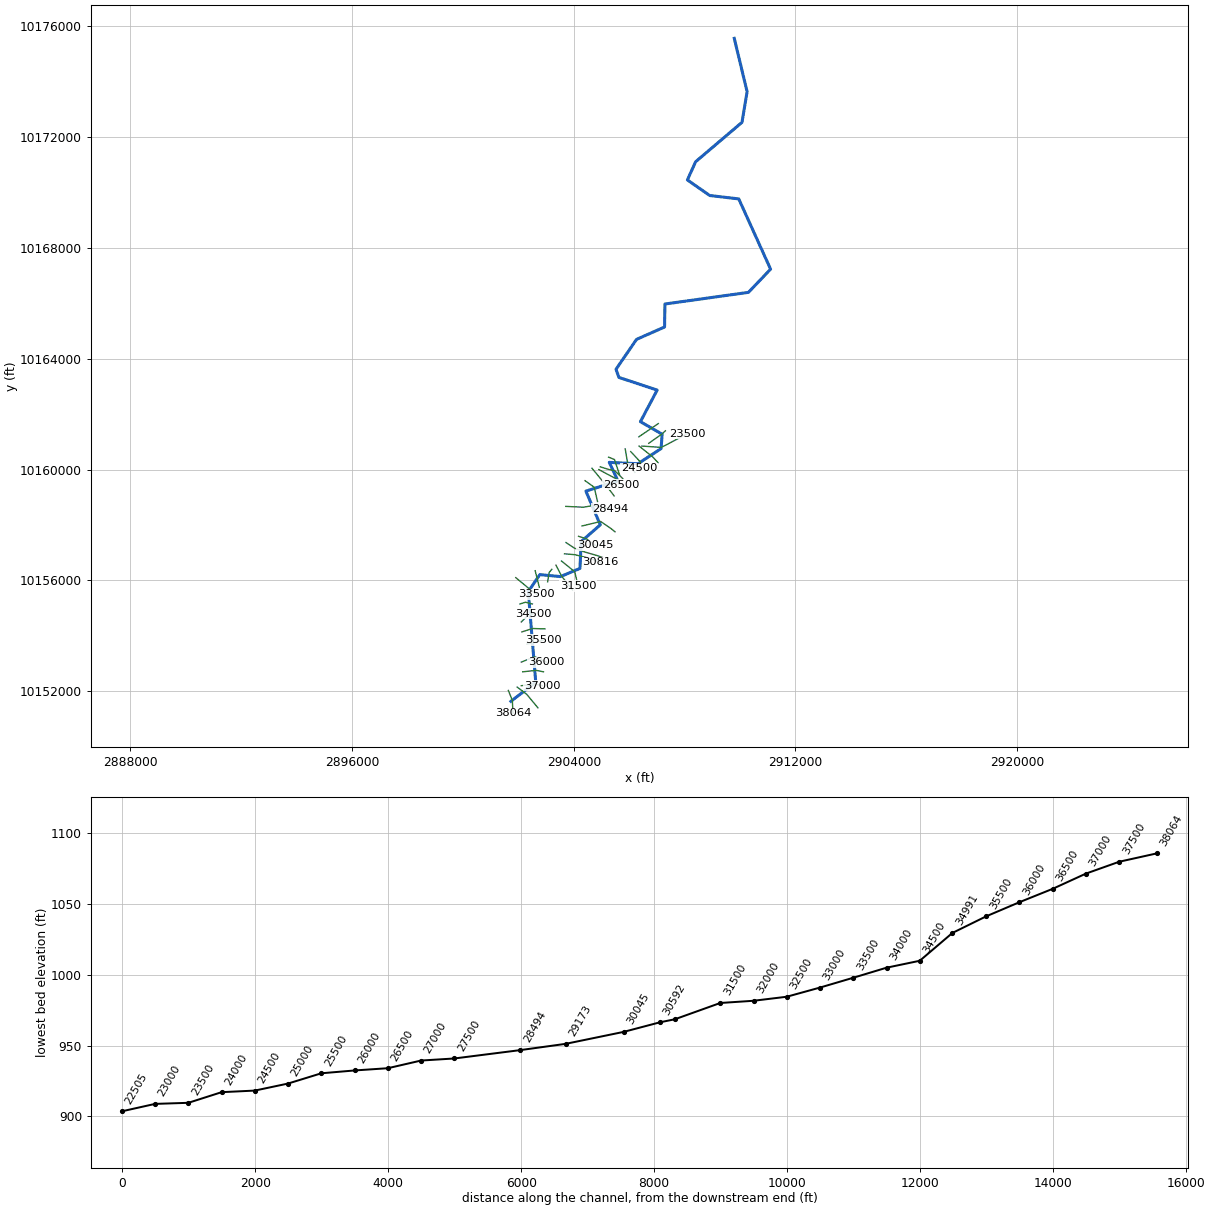
--- PECAN CREEK.prj (project) ---

Proj Title=PECAN CREEK Base Level Engineering
Current Plan=p01
Default Exp/Contr=0.3,0.1
English Units
Geom File=g01
Flow File=f01
Plan File=p01
BEGIN DESCRIPTION:
PECAN CREEK
END DESCRIPTION:

--- PECAN CREEK.p01 (plan) ---

Plan Title=Multiple Run
Short Identifier=Multiple
Geom File=g01
Flow File=f01
Subcritical Flow
K Sum by GR= 0
Std Step Tol= 0.01
Critical Tol= 0.01
Num of Std Step Trials= 20
Max Error Tol= 0.3
Flow Tol Ratio= 0.001
Split Flow NTrial= 30
Split Flow Tol= 0.02
Split Flow Ratio= 0.02
Log Output Level= 0
Friction Slope Method= 1
Unsteady Friction Slope Method= 2
Unsteady Bridges Friction Slope Method= 1
Parabolic Critical Depth
Global Vel Dist=  1 , 1 , 1
Global Log Level= 0
CheckData=True
Encroach Param= -1, 0, 0, 0
BEGIN DESCRIPTION:
Multiple Run
END DESCRIPTION:

--- PECAN CREEK.f01 (steady flow) ---

Flow Title=Multiple
Program Version=4.10
Number of Profiles= 7
Profile Names=10-year,25-year,50-year,1pct_min,100-year,1pct_plu,500-year
River Rch & RM=PECAN CREEK,Reach-1         ,38064
    1977    3537    7425    5275   10920   22605   15616
River Rch & RM=PECAN CREEK,Reach-1         ,30816
    2253    4081    8278    5710   12202   26074   17437
River Rch & RM=PECAN CREEK,Reach-1         ,23500
    3402    6354   12543    8622   18548   39900   26077
River Rch & RM=PECAN CREEK,Reach-1         ,18500
    5477   10431   19266   13059   28329   61453   38991
River Rch & RM=PECAN CREEK,Reach-1         ,13000
    5862   11181   20437   13806   30012   65241   41179
River Rch & RM=PECAN CREEK,Reach-1         ,12000
    5985   11428   20666   13771   30343   66857   41585
River Rch & RM=PECAN CREEK,Reach-1         ,7000
    6046   11556   20614   13565   30242   67426   41372
Boundary for River Rch & Prof#=PECAN CREEK,Reach-1         , 1
Up Type= 0
Dn Type= 3
Dn Slope=0.0005
Boundary for River Rch & Prof#=PECAN CREEK,Reach-1         , 2
Up Type= 0
Dn Type= 3
Dn Slope=0.0005
Boundary for River Rch & Prof#=PECAN CREEK,Reach-1         , 3
Up Type= 0
Dn Type= 3
Dn Slope=0.0005
Boundary for River Rch & Prof#=PECAN CREEK,Reach-1         , 4
Up Type= 0
Dn Type= 3
Dn Slope=0.0005
Boundary for River Rch & Prof#=PECAN CREEK,Reach-1         , 5
Up Type= 0
Dn Type= 3
Dn Slope=0.0005
Boundary for River Rch & Prof#=PECAN CREEK,Reach-1         , 6
Up Type= 0
Dn Type= 3
Dn Slope=0.0005
Boundary for River Rch & Prof#=PECAN CREEK,Reach-1         , 7
Up Type= 0
Dn Type= 3
Dn Slope=0.0005
DSS Import GetInterval= 0
DSS Import GetPeak= 0
DSS Import FillOption= 0

--- PECAN CREEK.g01 (geometry) ---

Geom Title=Existing Conditions

River Reach=PECAN CREEK,Reach-1
Reach XY= 30
      2901730.50     10151639.00      2902627.00     10152326.00
      2902357.25     10155598.00      2902773.25     10156212.00
      2903518.50     10156141.00      2904222.25     10156436.00
      2904268.75     10157407.00      2904955.50     10158009.00
      2904437.25     10159226.00      2905592.50     10159598.00
      2905280.00     10160264.00      2906315.75     10160215.00
      2907150.50     10160762.00      2907189.00     10161281.00
      2906404.25     10161733.00      2907009.25     10162874.00
      2905629.75     10163330.00      2905522.75     10163624.00
      2906263.75     10164704.00      2907275.75     10165151.00
      2907289.00     10165981.00      2910303.50     10166402.00
      2911102.50     10167239.00      2909954.50     10169775.00
      2908906.50     10169898.00      2908099.25     10170460.00
      2908397.00     10171117.00      2910070.75     10172540.00
      2910254.75     10173648.00      2909791.50     10175572.00

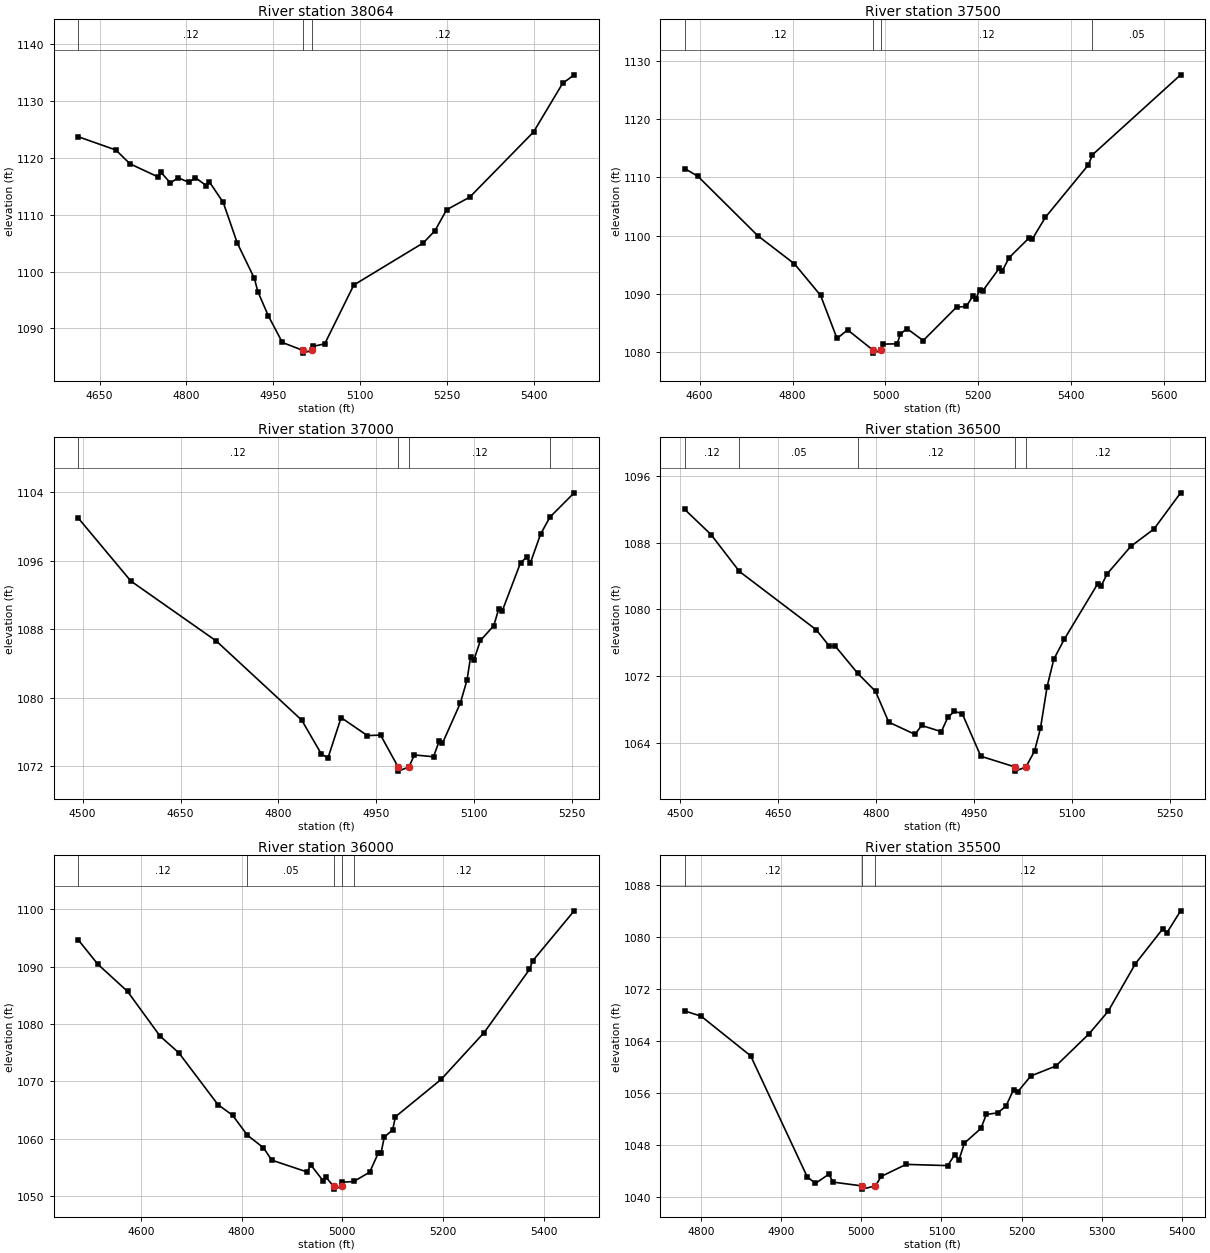
Type RM Length L Ch R = 1,38064,564,564,564
BEGIN DESCRIPTION:
PECAN CREEK 76.0
END DESCRIPTION:
XS GIS Cut Line= 3
      2901637.40     10152030.64      2901781.75     10151672.00
      2901805.68     10151203.11
#Sta/Elev= 30
  4613.4 1123.68  4678.3 1121.35  4702.5 1118.93  4750.8 1116.64  4756.2 1117.41
  4772.4 1115.57  4785.7 1116.47  4804.5 1115.68  4815.5 1116.49  4834.1 1115.11
  4839.5 1115.78  4863.6 1112.14  4887.8 1105.02  4917.4 1098.79  4923.3 1096.49
  4941.5 1092.21  4965.7 1087.54  5000.6 1086.17  5001.1 1085.67  5017.2 1086.17
  5018.9 1086.86  5038.9 1087.31  5089.0 1097.63  5209.2 1105.05  5229.2 1107.18
  5249.2 1110.85  5289.3 1113.08  5399.4 1124.52  5449.5 1133.05  5469.5 1134.56
#Mann=3,-1,0
  4613.4    0.12       0  5000.6    0.07       0  5017.2    0.12       0
Bank Sta=5000.6,5017.2
Exp/Cntr=0.3,0.1

Type RM Length L Ch R = 1,37500,500,500,500
BEGIN DESCRIPTION:
PECAN CREEK 75.0
END DESCRIPTION:
XS GIS Cut Line= 3
      2901955.71     10152153.09      2902300.25     10151892.49
      2902705.68     10151403.12
#Sta/Elev= 30
  4568.0 1111.50  4596.1 1110.19  4725.1 1099.97  4804.1 1095.13  4860.3 1089.72
  4895.7 1082.31  4918.6 1083.78  4973.4 1080.29  4973.9 1079.79  4990.1 1080.29
  4995.3 1081.34  5025.2 1081.39  5031.8 1083.02  5046.2 1084.01  5081.3 1081.95
  5153.0 1087.69  5173.8 1087.81  5188.1 1089.56  5194.6 1089.09  5202.5 1090.60
  5209.0 1090.44  5245.5 1094.43  5251.9 1093.98  5266.3 1096.20  5309.3 1099.60
  5315.8 1099.34  5344.4 1103.14  5436.9 1112.14  5445.7 1113.88  5635.5 1127.62
#Mann=4,-1,0
  4568.0    0.12       0  4973.4    0.07       0  4990.1    0.12       0
  5445.7    0.05       0
Bank Sta=4973.4,4990.1
Exp/Cntr=0.3,0.1

Type RM Length L Ch R = 1,37000,500,500,500
BEGIN DESCRIPTION:
PECAN CREEK 74.0
END DESCRIPTION:
XS GIS Cut Line= 3
      2902105.66     10152203.11      2902609.07     10152259.04
      2902855.70     10152203.11
#Sta/Elev= 30
  4493.5 1100.97  4574.0 1093.62  4704.8 1086.62  4835.6 1077.38  4865.8 1073.41
  4875.9 1072.97  4896.0 1077.67  4936.2 1075.57  4956.4 1075.63  4983.2 1071.92
  4983.7 1071.42  5000.0 1071.92  5008.1 1073.31  5037.5 1073.10  5046.1 1074.91
  5051.2 1074.68  5078.6 1079.37  5088.8 1082.06  5094.3 1084.76  5099.4 1084.42
  5109.3 1086.68  5129.8 1088.41  5137.4 1090.39  5142.5 1090.08  5170.9 1095.79
  5180.5 1096.41  5185.6 1095.69  5201.6 1099.13  5216.0 1101.11  5252.9 1103.93
#Mann=4,-1,0
  4493.5    0.12       0  4983.2    0.07       0  5000.0    0.12       0
  5216.0    0.05       0
Bank Sta=4983.2,5000
Exp/Cntr=0.3,0.1

Type RM Length L Ch R = 1,36500,500,500,500
BEGIN DESCRIPTION:
PECAN CREEK 73.0
END DESCRIPTION:
XS GIS Cut Line= 3
      2902155.71     10152703.11      2902645.19     10152755.74
      2902905.72     10152703.10
#Sta/Elev= 30
  4507.7 1091.95  4547.9 1088.94  4591.2 1084.54  4708.8 1077.56  4728.9 1075.59
  4737.8 1075.61  4772.2 1072.35  4799.3 1070.21  4819.5 1066.53  4859.7 1065.06
  4869.8 1066.13  4899.9 1065.39  4910.0 1067.12  4920.0 1067.81  4931.9 1067.54
  4960.3 1062.45  5012.5 1061.17  5013.0 1060.67  5029.3 1061.17  5042.5 1063.08
  5051.5 1065.79  5061.7 1070.78  5071.9 1074.05  5088.1 1076.46  5138.9 1083.05
  5144.0 1082.76  5153.5 1084.26  5189.6 1087.54  5225.0 1089.61  5265.8 1093.94
#Mann=5,-1,0
  4507.7    0.12       0  4591.2    0.05       0  4772.2    0.12       0
  5012.5    0.07       0  5029.3    0.12       0
Bank Sta=5012.5,5029.3
Exp/Cntr=0.3,0.1

Type RM Length L Ch R = 1,36000,500,500,500
BEGIN DESCRIPTION:
PECAN CREEK 72.0
END DESCRIPTION:
XS GIS Cut Line= 3
      2902105.72     10153053.12      2902590.65     10153250.87
      2903005.65     10153053.13
#Sta/Elev= 30
  4476.3 1094.66  4515.0 1090.43  4573.9 1085.69  4638.3 1077.91  4675.5 1075.00
  4753.0 1065.98  4782.4 1064.09  4811.5 1060.64  4843.4 1058.44  4860.0 1056.28
  4929.8 1054.23  4937.5 1055.43  4961.5 1052.72  4966.9 1053.36  4982.5 1051.73
  4983.0 1051.23  4999.4 1051.73  5000.0 1052.44  5022.5 1052.56  5054.2 1054.19
  5071.3 1057.54  5076.9 1057.61  5083.1 1060.30  5099.6 1061.55  5105.3 1063.85
  5195.9 1070.36  5281.2 1078.53  5371.1 1089.52  5377.5 1091.02  5459.7 1099.74
#Mann=5,-1,0
  4476.3    0.12       0  4811.5    0.05       0  4982.5    0.05       0
  4999.4    0.05       0  5022.5    0.12       0
Bank Sta=4982.5,4999.4
Exp/Cntr=0.3,0.1

Type RM Length L Ch R = 1,35500,509,509,509
BEGIN DESCRIPTION:
PECAN CREEK 71.0
END DESCRIPTION:
XS GIS Cut Line= 3
      2902305.64     10153703.10      2902521.89     10153745.66
      2902905.73     10153853.12
#Sta/Elev= 30
  4779.6 1068.68  4800.0 1067.87  4861.8 1061.77  4932.5 1043.13  4942.7 1042.13
  4959.5 1043.55  4964.6 1042.33  5000.6 1041.75  5001.1 1041.25  5017.6 1041.75
  5024.7 1043.20  5055.9 1045.06  5107.8 1044.87  5116.7 1046.58  5121.9 1045.74
  5128.6 1048.32  5149.3 1050.60  5156.0 1052.74  5170.1 1052.99  5180.5 1054.01
  5190.1 1056.58  5195.3 1056.24  5211.6 1058.67  5242.8 1060.20  5284.3 1065.16
  5308.1 1068.62  5342.2 1075.96  5376.3 1081.32  5381.5 1080.72  5398.6 1084.09
#Mann=3,-1,0
  4779.6    0.12       0  5000.6    0.07       0  5017.6    0.12       0
Bank Sta=5000.6,5017.6
Exp/Cntr=0.3,0.1

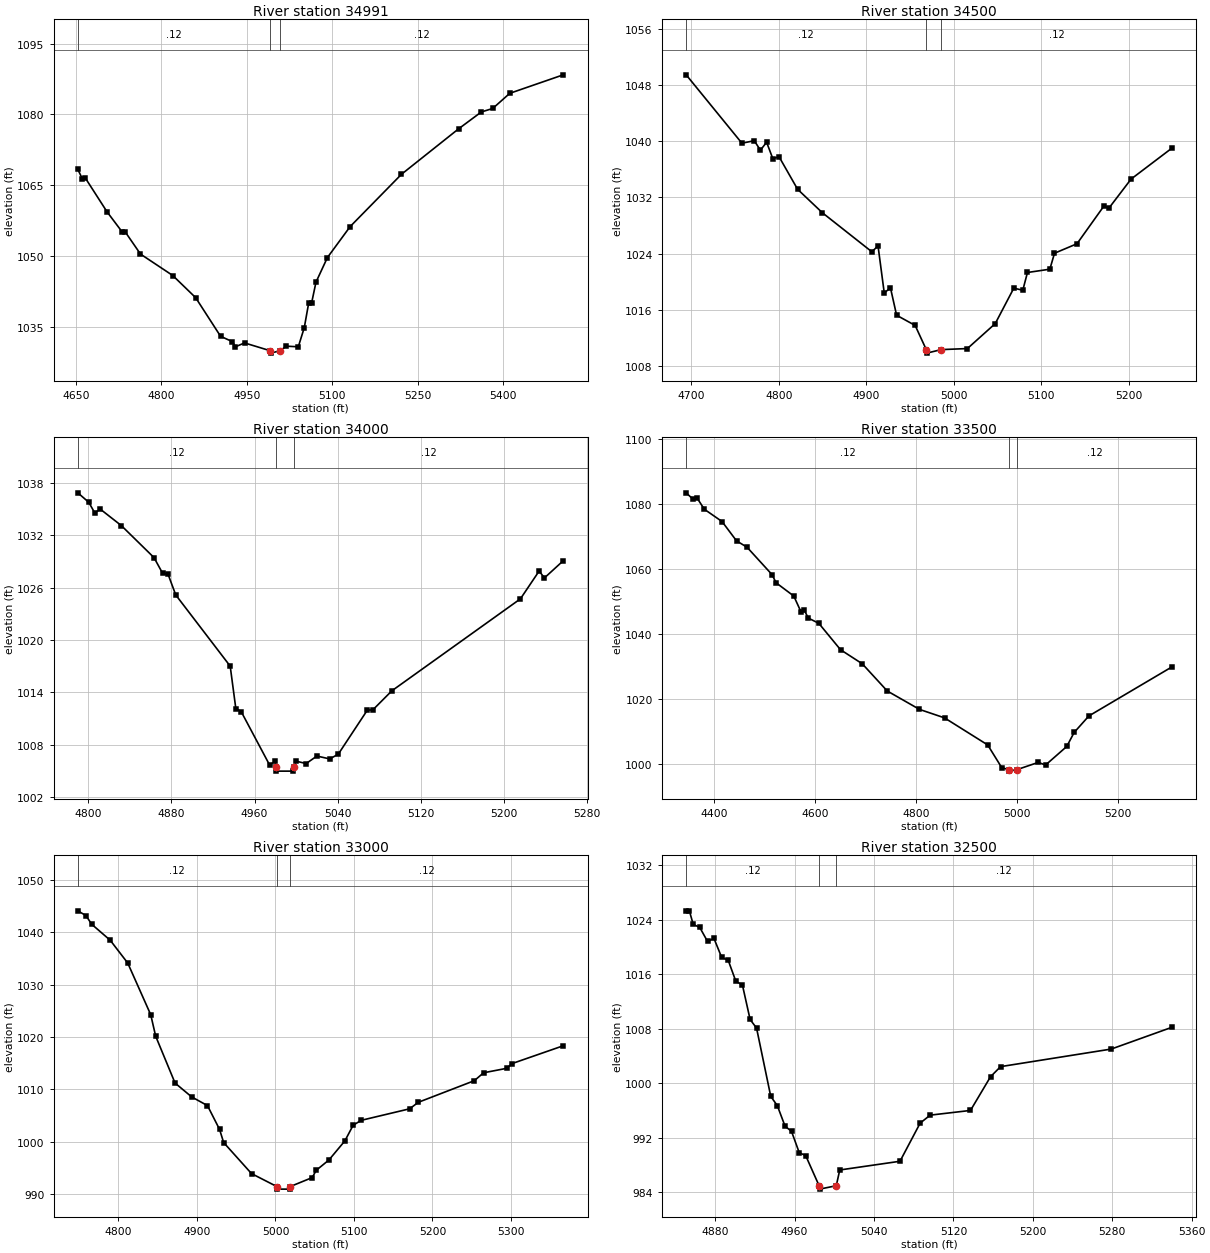
Type RM Length L Ch R = 1,34991,491,491,491
BEGIN DESCRIPTION:
Mapping XS 6651c103
END DESCRIPTION:
XS GIS Cut Line= 3
      2902126.79     10154144.51      2902515.35     10154267.86
      2902959.41     10154252.44
#Sta/Elev= 30
  4653.6 1068.37  4661.6 1066.39  4666.8 1066.55  4704.9 1059.40  4731.4 1055.15
  4736.6 1055.19  4763.6 1050.46  4820.3 1045.92  4860.4 1041.24  4904.2 1033.06
  4924.9 1031.93  4930.2 1030.84  4946.2 1031.66  4991.5 1030.00  4992.0 1029.50
  5008.5 1030.00  5019.7 1030.97  5040.6 1030.84  5051.1 1034.91  5058.8 1040.09
  5063.9 1040.09  5071.6 1044.51  5091.6 1049.71  5131.6 1056.28  5221.7 1067.35
  5321.8 1076.95  5361.8 1080.53  5381.8 1081.27  5411.8 1084.48  5505.6 1088.39
#Mann=3,-1,0
  4653.6    0.12       0  4991.5    0.07       0  5008.5    0.12       0
Bank Sta=4991.5,5008.5
Exp/Cntr=0.3,0.1

Type RM Length L Ch R = 1,34500,500,500,500
BEGIN DESCRIPTION:
PECAN CREEK 69.0
END DESCRIPTION:
XS GIS Cut Line= 3
      2902105.67     10154503.10      2902321.08     10154720.16
      2902555.65     10154803.10
#Sta/Elev= 30
  4694.2 1049.44  4757.9 1039.71  4772.0 1040.07  4779.0 1038.72  4786.1 1039.85
  4793.2 1037.51  4800.3 1037.79  4821.5 1033.16  4849.8 1029.82  4906.3 1024.27
  4913.4 1025.10  4920.5 1018.41  4927.6 1019.14  4934.6 1015.24  4955.8 1013.79
  4968.5 1010.35  4969.0 1009.85  4985.6 1010.35  5015.5 1010.50  5047.3 1014.05
  5068.5 1019.09  5078.8 1018.80  5084.1 1021.32  5109.7 1021.79  5115.0 1024.06
  5140.7 1025.41  5171.6 1030.80  5176.9 1030.43  5202.5 1034.61  5248.8 1038.98
#Mann=3,-1,0
  4694.2    0.12       0  4968.5    0.07       0  4985.6    0.12       0
Bank Sta=4968.5,4985.6
Exp/Cntr=0.3,0.1

Type RM Length L Ch R = 1,34000,500,500,500
BEGIN DESCRIPTION:
PECAN CREEK 68.0
END DESCRIPTION:
XS GIS Cut Line= 3
      2902055.67     10155153.11      2902256.28     10155215.20
      2902505.67     10155153.12
#Sta/Elev= 30
  4790.0 1036.87  4800.5 1035.79  4806.3 1034.57  4811.6 1035.00  4831.9 1033.11
  4863.3 1029.44  4871.5 1027.66  4876.8 1027.54  4884.2 1025.16  4936.6 1016.99
  4942.0 1012.13  4947.2 1011.77  4974.6 1005.63  4979.9 1006.10  4980.4 1005.45
  4980.9 1004.95  4997.0 1004.95  4997.5 1005.45  5000.0 1006.09  5009.7 1005.82
  5020.0 1006.68  5032.4 1006.35  5040.6 1006.90  5068.6 1011.96  5073.7 1011.96
  5092.1 1014.16  5215.8 1024.71  5233.8 1027.90  5238.9 1027.11  5257.0 1029.08
#Mann=3,-1,0
  4790.0    0.12       0  4980.4    0.07       0  4997.5    0.12       0
Bank Sta=4980.4,4997.5
Exp/Cntr=0.3,0.1

Type RM Length L Ch R = 1,33500,500,500,500
BEGIN DESCRIPTION:
PECAN CREEK 67.0
END DESCRIPTION:
XS GIS Cut Line= 3
      2901905.66     10156103.14      2902410.63     10155685.81
      2902655.71     10155503.09
#Sta/Elev= 30
  4344.9 1083.43  4358.6 1081.44  4366.4 1081.85  4380.8 1078.39  4415.9 1074.60
  4444.6 1068.66  4465.4 1066.70  4514.9 1058.27  4522.8 1055.78  4557.9 1051.69
  4572.3 1046.79  4578.7 1047.34  4586.6 1044.92  4607.4 1043.31  4650.4 1035.19
  4693.4 1030.87  4742.9 1022.50  4806.7 1016.84  4856.2 1014.24  4941.7 1005.91
  4969.6  998.90  4983.1  998.36  4983.6  997.86  5000.4  998.36  5041.9 1000.55
  5056.2  999.73  5098.2 1005.45  5112.8 1009.75  5142.0 1014.83  5305.7 1029.85
#Mann=3,-1,0
  4344.9    0.12       0  4983.1    0.07       0  5000.4    0.12       0
Bank Sta=4983.1,5000.4
Exp/Cntr=0.3,0.1

Type RM Length L Ch R = 1,33000,500,500,500
BEGIN DESCRIPTION:
PECAN CREEK 66.0
END DESCRIPTION:
XS GIS Cut Line= 3
      2902605.69     10156353.09      2902668.47     10156109.24
      2902755.69     10155753.07
#Sta/Elev= 30
  4748.2 1044.08  4758.5 1043.18  4766.0 1041.50  4789.5 1038.46  4811.8 1034.11
  4841.1 1024.24  4847.4 1020.14  4872.1 1011.19  4893.2 1008.55  4913.4 1006.88
  4928.8 1002.34  4934.0  999.83  4969.5  993.90  5001.7  991.43  5002.2  990.93
  5018.5  990.93  5019.0  991.43  5046.8  993.13  5052.0  994.53  5068.1  996.49
  5088.5 1000.15  5099.0 1003.13  5109.3 1004.07  5171.0 1006.27  5182.0 1007.51
  5253.4 1011.64  5265.2 1013.15  5294.6 1014.00  5301.7 1014.92  5366.7 1018.31
#Mann=3,-1,0
  4748.2    0.12       0  5001.7    0.07       0  5019.0    0.12       0
Bank Sta=5001.7,5019
Exp/Cntr=0.3,0.1

Type RM Length L Ch R = 1,32500,500,500,500
BEGIN DESCRIPTION:
PECAN CREEK 65.0
END DESCRIPTION:
XS GIS Cut Line= 3
      2903205.68     10156403.10      2903110.15     10156288.49
      2903055.68     10155953.09
#Sta/Elev= 30
  4850.8 1025.30  4854.0 1025.30  4857.9 1023.31  4864.5 1022.86  4872.3 1020.81
  4878.8 1021.25  4886.6 1018.45  4893.1 1018.06  4900.9 1014.93  4907.4 1014.45
  4915.2 1009.35  4921.7 1008.09  4936.0  998.06  4942.6  996.71  4950.4  993.69
  4956.9  992.93  4964.7  989.80  4971.2  989.37  4984.7  984.95  4985.2  984.45
  5002.0  984.95  5005.5  987.26  5066.2  988.54  5086.5  994.14  5096.6  995.31
  5137.2  996.00  5157.4 1000.95  5167.5 1002.43  5279.0 1005.01  5339.8 1008.19
#Mann=3,-1,0
  4850.8    0.12       0  4984.7    0.07       0  5002.0    0.12       0
Bank Sta=4984.7,5002
Exp/Cntr=0.3,0.1

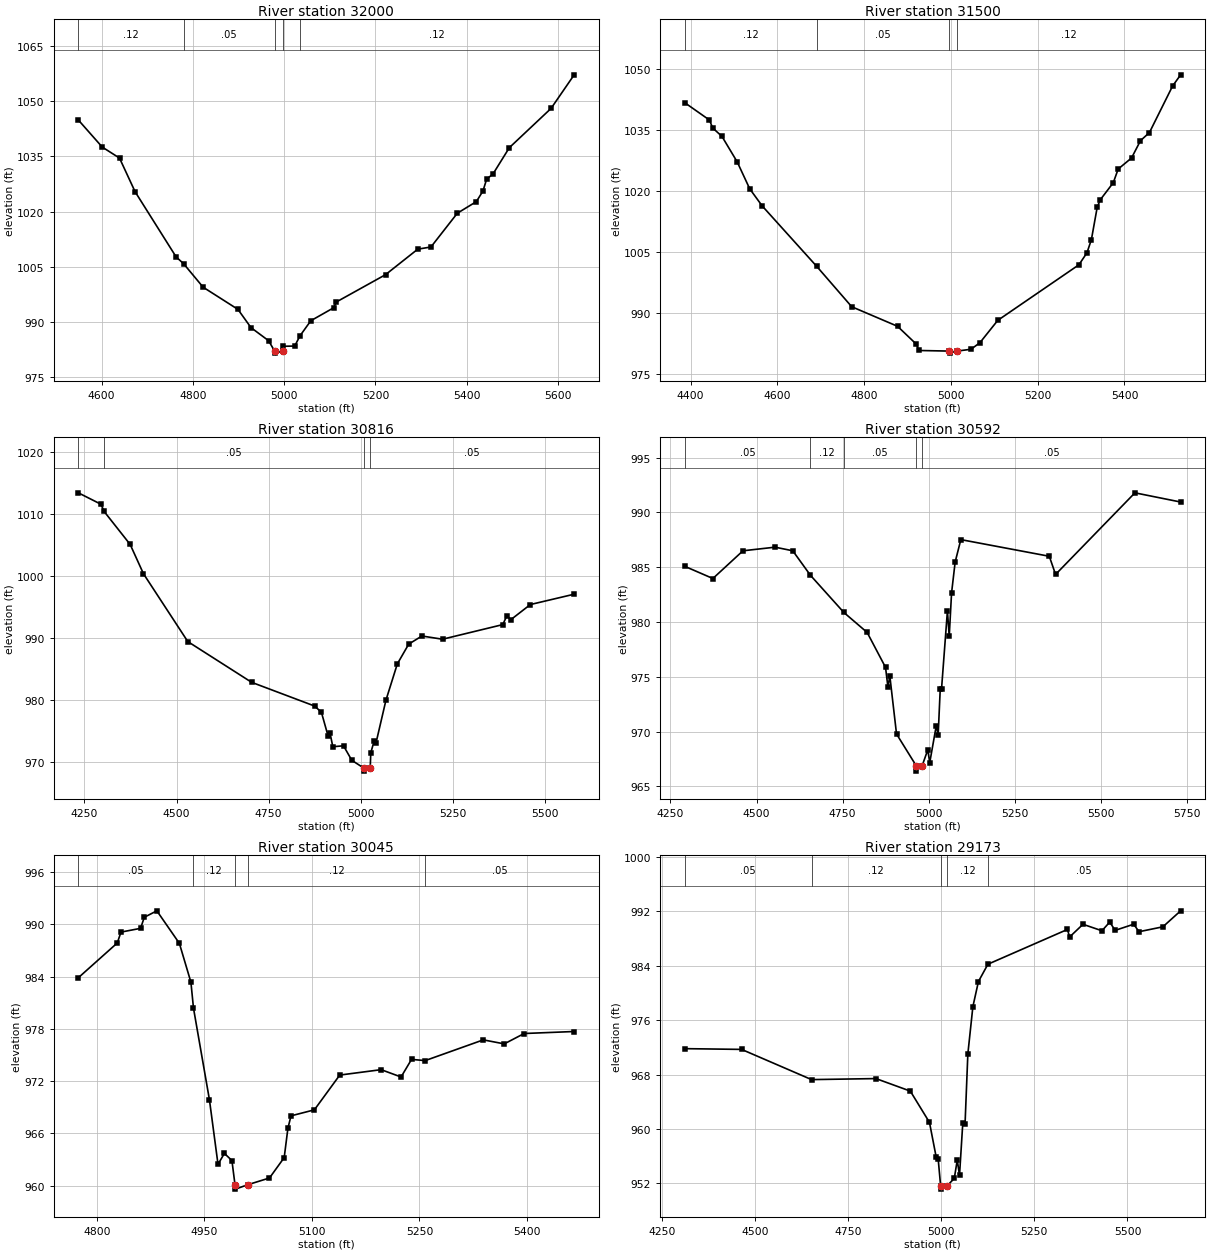
Type RM Length L Ch R = 1,32000,500,500,500
BEGIN DESCRIPTION:
PECAN CREEK 64.0
END DESCRIPTION:
XS GIS Cut Line= 3
      2903355.68     10156553.11      2903564.04     10156153.35
      2903955.67     10155653.12
#Sta/Elev= 30
  4549.2 1044.84  4601.6 1037.49  4639.4 1034.51  4673.5 1025.39  4763.5 1007.68
  4779.6 1005.88  4822.6  999.48  4898.8  993.47  4927.4  988.52  4966.0  984.97
  4979.4  982.10  4979.9  981.60  4996.8  982.10  4997.3  983.46  5023.2  983.52
  5034.7  986.29  5058.5  990.39  5108.2  993.88  5114.6  995.49  5222.1 1002.88
  5292.7 1009.80  5321.6 1010.39  5379.4 1019.55  5421.0 1022.69  5435.5 1025.57
  5443.6 1028.79  5457.5 1030.19  5493.3 1037.33  5584.7 1047.98  5635.3 1057.09
#Mann=5,-1,0
  4549.2    0.12       0  4779.6    0.05       0  4979.4    0.03       0
  4996.8    0.05       0  5034.7    0.12       0
Bank Sta=4979.4,4996.8
Exp/Cntr=0.3,0.1

Type RM Length L Ch R = 1,31500,684,684,684
BEGIN DESCRIPTION:
PECAN CREEK 63.0
END DESCRIPTION:
XS GIS Cut Line= 3
      2903555.67     10156703.12      2904033.11     10156318.16
      2904155.68     10155803.15
#Sta/Elev= 30
  4386.7 1041.63  4443.5 1037.37  4450.9 1035.43  4472.3 1033.35  4507.5 1027.07
  4536.3 1020.46  4565.0 1016.25  4690.8 1001.37  4771.4  991.45  4877.0  986.64
  4920.1  982.26  4926.5  980.69  4996.4  980.54  4996.9  980.04  5013.9  980.54
  5046.3  980.99  5066.9  982.61  5108.0  988.10  5295.0 1001.77  5313.6 1004.73
  5323.8 1007.98  5337.2 1015.95  5344.4 1017.78  5374.2 1021.96  5385.5 1025.32
  5416.3 1028.04  5436.9 1032.30  5457.5 1034.29  5510.9 1045.74  5529.4 1048.49
#Mann=4,-1,0
  4386.7    0.12       0  4690.8    0.05       0  4996.4    0.07       0
  5013.9    0.12       0
Bank Sta=4996.4,5013.9
Exp/Cntr=0.3,0.1

Type RM Length L Ch R = 1,30816,224,224,224
BEGIN DESCRIPTION:
Mapping XS e553dc2b
END DESCRIPTION:
XS GIS Cut Line= 4
      2903665.48     10156962.86      2904035.53     10156932.03
      2904587.48     10156796.35      2904966.73     10156651.44
#Sta/Elev= 30
  4233.5 1013.47  4294.8 1011.63  4303.5 1010.46  4374.2 1005.13  4410.2 1000.41
  4530.6  989.45  4703.9  982.87  4875.2  979.03  4893.3  978.02  4911.6  974.14
  4916.8  974.62  4924.2  972.47  4953.2  972.62  4975.7  970.28  5008.1  969.03
  5008.6  968.53  5025.7  969.03  5027.2  971.48  5036.2  973.37  5041.4  973.08
  5068.4  979.99  5099.3  985.85  5130.2  989.04  5166.0  990.35  5221.9  989.83
  5385.4  992.19  5396.9  993.65  5406.8  992.96  5460.3  995.43  5579.2  997.10
#Mann=4,-1,0
  4233.5    0.12       0  4303.5    0.05       0  5008.1    0.05       0
  5025.7    0.05       0
Bank Sta=5008.1,5025.7
Exp/Cntr=0.3,0.1

Type RM Length L Ch R = 1,30592,547,547,547
BEGIN DESCRIPTION:
Mapping XS 5e59f4ac
END DESCRIPTION:
XS GIS Cut Line= 5
      2903717.96     10157369.87      2904026.28     10157166.37
      2904377.80     10157033.78      2904849.58     10156898.11
      2905040.69     10156830.29
#Sta/Elev= 30
  4291.9  985.08  4373.4  983.97  4460.7  986.50  4554.0  986.83  4605.2  986.50
  4656.6  984.26  4753.5  980.87  4821.0  979.05  4874.4  975.86  4881.4  974.05
  4886.8  975.09  4906.3  969.78  4963.2  966.89  4963.7  966.39  4980.8  966.89
  4996.9  968.33  5002.7  967.17  5021.7  970.55  5027.1  969.66  5033.2  973.93
  5037.0  973.93  5054.0  981.02  5059.2  978.68  5066.0  982.65  5076.4  985.47
  5092.9  987.52  5349.6  986.00  5367.8  984.34  5598.1  991.79  5730.7  990.95
#Mann=5,-1,0
  4291.9    0.05       0  4656.6    0.12       0  4753.5    0.05       0
  4963.2    0.03       0  4980.8    0.05       0
Bank Sta=4963.2,4980.8
Exp/Cntr=0.3,0.1

Type RM Length L Ch R = 1,30045,872,872,872
BEGIN DESCRIPTION:
Mapping XS 8003550b
END DESCRIPTION:
XS GIS Cut Line= 3
      2904171.19     10157594.99      2904457.97     10157505.56
      2904771.59     10157271.88
#Sta/Elev= 30
  4774.3  983.87  4828.6  987.86  4833.8  989.11  4861.1  989.54  4866.3  990.81
  4883.8  991.55  4915.2  987.82  4931.3  983.36  4934.9  980.38  4957.1  969.89
  4969.1  962.46  4978.0  963.71  4988.5  962.89  4992.8  960.11  4993.3  959.61
  5010.4  960.11  5040.9  960.89  5061.4  963.23  5066.6  966.60  5070.9  968.02
  5103.5  968.71  5138.9  972.70  5196.6  973.32  5224.4  972.48  5239.0  974.50
  5258.0  974.36  5339.1  976.74  5368.3  976.28  5396.1  977.47  5465.8  977.70
#Mann=5,-1,0
  4774.3    0.05       0  4934.9    0.12       0  4992.8    0.07       0
  5010.4    0.12       0  5258.0    0.05       0
Bank Sta=4992.8,5010.4
Exp/Cntr=0.3,0.1

Type RM Length L Ch R = 1,29173,679,679,679
BEGIN DESCRIPTION:
Mapping XS 3542c70d
END DESCRIPTION:
XS GIS Cut Line= 4
      2904297.62     10157968.09      2904969.84     10158131.52
      2905346.03     10157872.50      2905487.90     10157758.39
#Sta/Elev= 30
  4312.1  971.82  4464.5  971.71  4652.3  967.27  4825.0  967.42  4917.3  965.58
  4968.7  960.98  4986.8  955.86  4992.0  955.65  4998.6  951.67  4999.1  951.17
  5016.3  951.67  5035.3  952.75  5043.3  955.45  5049.3  953.19  5058.1  960.88
  5064.2  960.77  5071.7  971.05  5085.2  978.00  5100.1  981.69  5125.5  984.23
  5338.8  989.34  5344.9  988.24  5380.7  990.10  5431.5  989.15  5452.4  990.42
  5467.1  989.21  5516.7  990.11  5531.1  989.01  5595.1  989.73  5642.7  992.08
#Mann=5,-1,0
  4312.1    0.05       0  4652.3    0.12       0  4998.6    0.07       0
  5016.3    0.12       0  5125.5    0.05       0
Bank Sta=4998.6,5016.3
Exp/Cntr=0.3,0.1

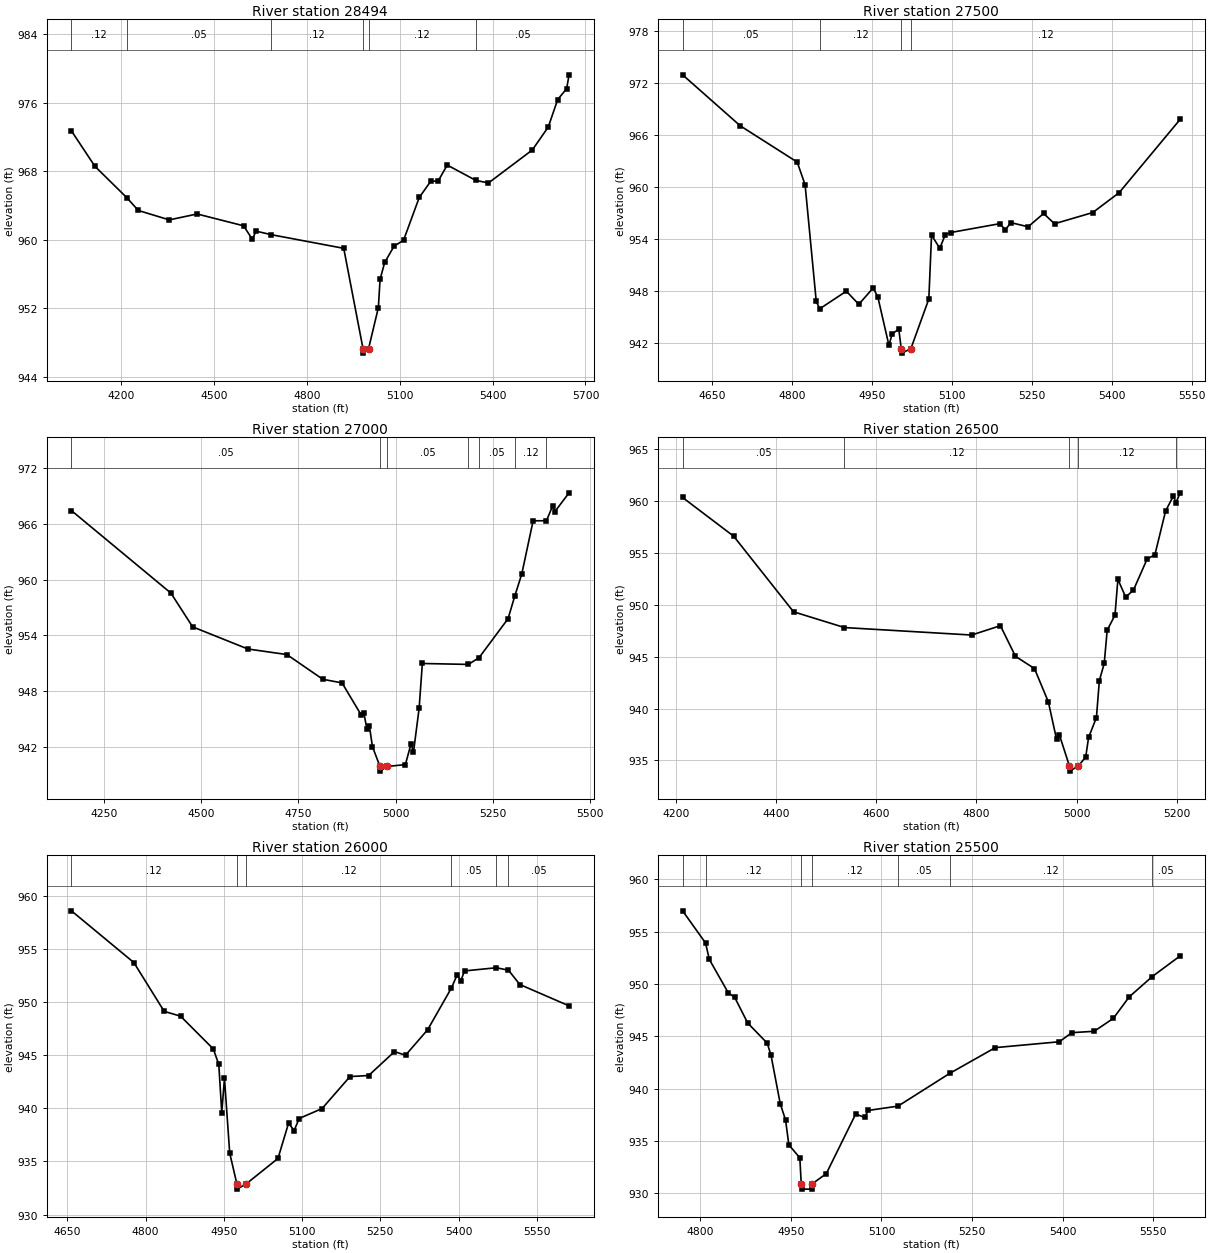
Type RM Length L Ch R = 1,28494,994,994,994
BEGIN DESCRIPTION:
Mapping XS 42d5c9a0
END DESCRIPTION:
XS GIS Cut Line= 4
      2903709.75     10158675.60      2904353.44     10158645.47
      2904701.57     10158708.14      2905301.81     10158597.32
#Sta/Elev= 30
  4038.5  972.71  4114.5  968.57  4217.6  964.91  4254.7  963.42  4354.8  962.32
  4444.9  963.01  4595.0  961.63  4623.3  960.05  4635.1  961.01  4683.5  960.60
  4918.7  959.00  4981.1  947.27  4981.6  946.77  4998.8  947.27  5030.6  952.08
  5036.1  955.37  5051.0  957.35  5081.5  959.26  5112.0  959.94  5162.8  964.94
  5200.2  966.84  5223.8  966.85  5253.2  968.72  5345.6  966.93  5386.5  966.63
  5528.2  970.48  5579.8  973.16  5610.3  976.37  5639.2  977.63  5647.0  979.25
#Mann=6,-1,0
  4038.5    0.12       0  4217.6    0.05       0  4683.5    0.12       0
  4981.1    0.07       0  4998.8    0.12       0  5345.6    0.05       0
Bank Sta=4981.1,4998.8
Exp/Cntr=0.3,0.1

Type RM Length L Ch R = 1,27500,500,500,500
BEGIN DESCRIPTION:
PECAN CREEK 55.0
END DESCRIPTION:
XS GIS Cut Line= 3
      2904405.67     10159603.12      2904736.87     10159368.14
      2904855.70     10158853.06
#Sta/Elev= 30
  4593.9  972.90  4702.2  967.03  4809.2  962.85  4824.0  960.24  4844.9  946.84
  4851.3  945.95  4901.5  947.98  4924.9  946.47  4951.9  948.36  4960.6  947.32
  4981.5  941.74  4987.6  943.08  5000.0  943.60  5004.6  941.35  5005.1  940.85
  5022.6  941.35  5056.4  947.08  5061.5  954.44  5077.0  952.92  5087.3  954.50
  5097.5  954.74  5189.8  955.76  5200.1  955.04  5210.4  955.88  5242.9  955.40
  5272.0  956.93  5292.5  955.75  5364.3  957.04  5413.9  959.33  5528.6  967.78
#Mann=4,-1,0
  4593.9    0.05       0  4851.3    0.12       0  5004.6    0.07       0
  5022.6    0.12       0
Bank Sta=5004.6,5022.6
Exp/Cntr=0.3,0.1

Type RM Length L Ch R = 1,27000,500,500,500
BEGIN DESCRIPTION:
PECAN CREEK 54.0
END DESCRIPTION:
XS GIS Cut Line= 3
      2904655.70     10160053.10      2905186.19     10159409.05
      2905455.66     10159053.15
#Sta/Elev= 30
  4165.6  967.42  4421.7  958.54  4477.6  954.91  4619.7  952.53  4720.1  951.93
  4812.6  949.27  4862.1  948.88  4911.6  945.42  4918.1  945.69  4925.9  943.95
  4932.4  944.29  4940.3  942.03  4959.8  939.89  4960.3  939.39  4977.8  939.89
  5025.1  940.09  5039.7  942.33  5046.0  941.43  5060.5  946.15  5068.8  950.97
  5187.3  950.87  5214.9  951.60  5289.4  955.79  5306.8  958.24  5324.7  960.60
  5353.9  966.32  5388.2  966.33  5403.8  967.88  5410.1  967.32  5446.4  969.33
#Mann=7,-1,0
  4165.6    0.05       0  4959.8    0.05       0  4977.8    0.05       0
  5187.3    0.12       0  5214.9    0.05       0  5306.8    0.12       0
  5388.2    0.05       0
Bank Sta=4959.8,4977.8
Exp/Cntr=0.3,0.1

Type RM Length L Ch R = 1,26500,500,500,500
BEGIN DESCRIPTION:
PECAN CREEK 53.0
END DESCRIPTION:
XS GIS Cut Line= 3
      2904905.72     10160003.09      2905599.73     10159631.35
      2905705.66     10159453.15
#Sta/Elev= 30
  4212.7  960.33  4314.8  956.60  4434.4  949.32  4536.3  947.80  4790.3  947.08
  4847.9  947.98  4878.0  945.03  4916.0  943.85  4943.8  940.63  4960.1  937.04
  4965.8  937.46  4985.8  934.47  4986.3  933.97  5003.9  934.47  5018.4  935.34
  5024.2  937.22  5039.8  939.13  5045.7  942.70  5055.4  944.34  5061.3  947.54
  5076.9  949.00  5082.7  952.45  5098.3  950.73  5113.9  951.42  5141.1  954.40
  5156.7  954.82  5178.1  959.04  5193.7  960.48  5198.6  959.82  5207.3  960.78
#Mann=5,-1,0
  4212.7    0.05       0  4536.3    0.12       0  4985.8    0.07       0
  5003.9    0.12       0  5198.6    0.05       0
Bank Sta=4985.8,5003.9
Exp/Cntr=0.3,0.1

Type RM Length L Ch R = 1,26000,500,500,500
BEGIN DESCRIPTION:
PECAN CREEK 52.0
END DESCRIPTION:
XS GIS Cut Line= 4
      2904955.64     10160103.12      2905282.78     10160002.37
      2905477.07     10159967.30      2905770.92     10159674.86
#Sta/Elev= 30
  4657.7  958.60  4777.4  953.73  4835.6  949.13  4867.0  948.68  4929.8  945.59
  4940.3  944.13  4946.0  939.59  4951.2  942.83  4961.2  935.80  4974.9  932.89
  4975.4  932.39  4993.0  932.89  5053.8  935.28  5074.1  938.60  5084.8  937.91
  5094.4  939.04  5138.4  939.98  5191.9  942.99  5227.7  943.09  5277.2  945.34
  5298.4  945.00  5340.8  947.40  5386.5  951.34  5397.4  952.57  5404.5  952.02
  5411.5  952.94  5472.6  953.24  5495.8  953.01  5517.6  951.66  5612.0  949.65
#Mann=6,-1,0
  4657.7    0.12       0  4974.9    0.07       0  4993.0    0.12       0
  5386.5    0.05       0  5472.6    0.12       0  5495.8    0.05       0
Bank Sta=4974.9,4993
Exp/Cntr=0.3,0.1

Type RM Length L Ch R = 1,25500,500,500,500
BEGIN DESCRIPTION:
PECAN CREEK 51.0
END DESCRIPTION:
XS GIS Cut Line= 3
      2905255.68     10160453.11      2905468.27     10160367.45
      2905655.67     10159803.15
#Sta/Elev= 30
  4770.8  956.98  4808.8  953.91  4815.1  952.33  4846.3  949.16  4857.1  948.71
  4878.6  946.26  4911.0  944.33  4917.2  943.17  4932.5  938.54  4941.3  936.99
  4946.7  934.62  4964.9  933.38  4967.2  930.89  4967.7  930.39  4984.8  930.39
  4985.3  930.89  5008.7  931.87  5057.3  937.56  5072.1  937.25  5078.3  937.91
  5127.4  938.32  5213.6  941.47  5288.5  943.91  5394.4  944.47  5415.2  945.34
  5452.1  945.47  5483.8  946.70  5510.2  948.76  5548.3  950.70  5594.6  952.68
#Mann=7,-1,0
  4770.8    0.05       0  4808.8    0.12       0  4967.2    0.07       0
  4985.3    0.12       0  5127.4    0.05       0  5213.6    0.12       0
  5548.3    0.05       0
Bank Sta=4967.2,4985.3
Exp/Cntr=0.3,0.1

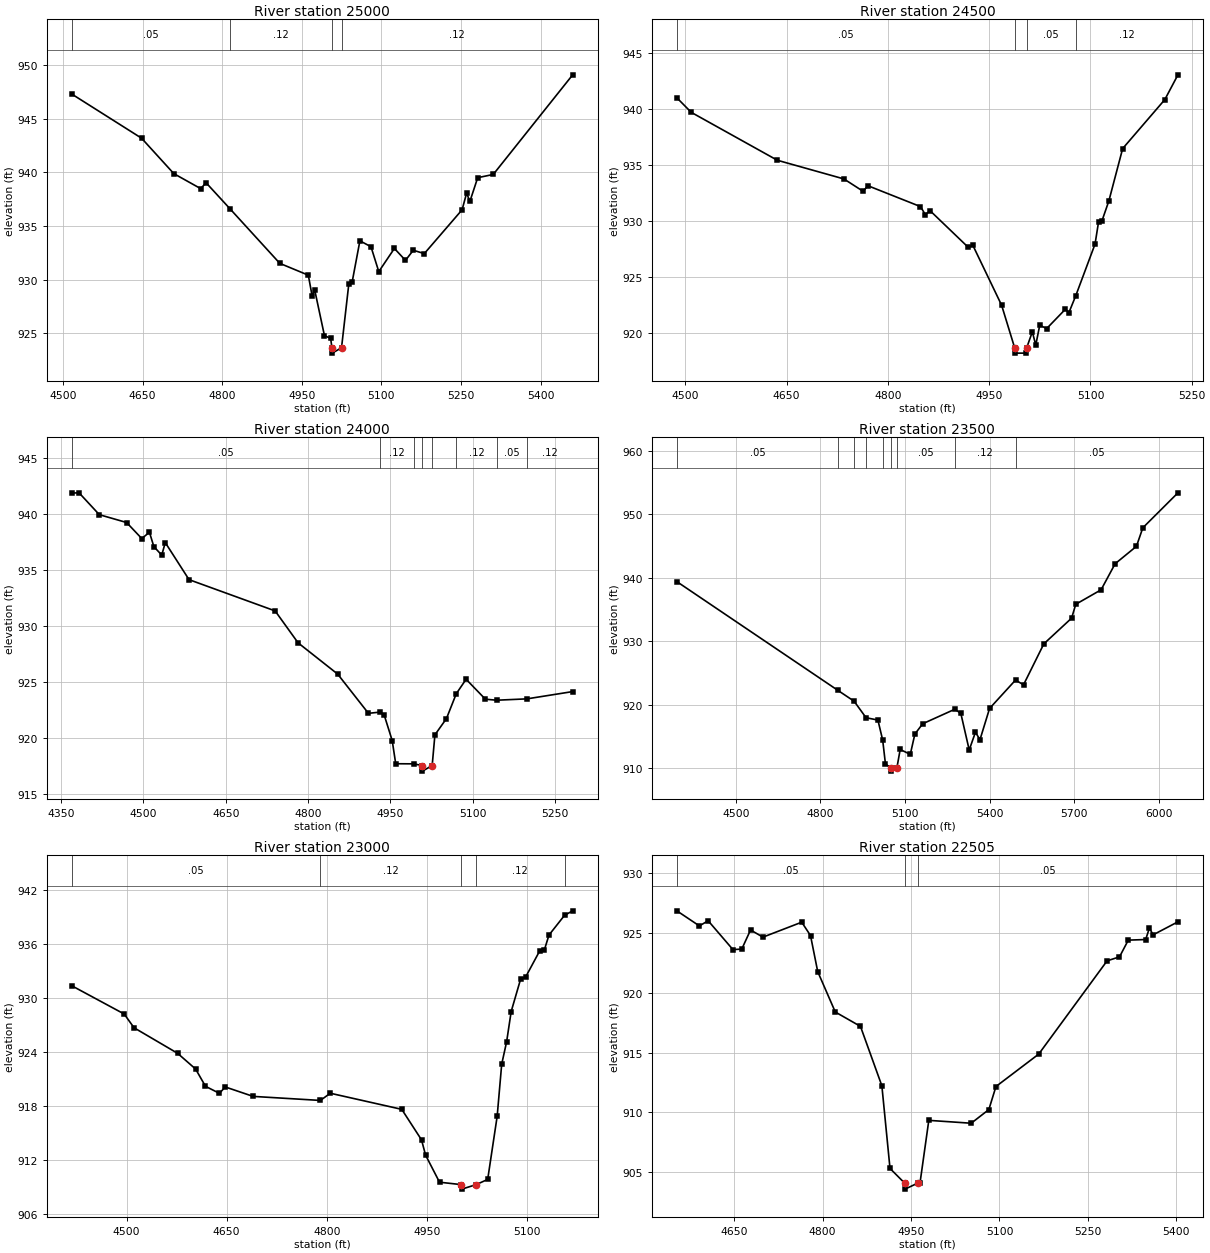
Type RM Length L Ch R = 1,25000,500,500,500
BEGIN DESCRIPTION:
PECAN CREEK 50.0
END DESCRIPTION:
XS GIS Cut Line= 3
      2905855.69     10160753.09      2905935.38     10160276.00
      2906205.71     10159903.07
#Sta/Elev= 30
  4516.3  947.29  4648.1  943.17  4708.9  939.87  4759.6  938.47  4769.7  939.02
  4815.6  936.55  4908.7  931.51  4962.4  930.41  4969.5  928.50  4974.5  929.02
  4992.8  924.78  5004.5  924.52  5006.9  923.65  5007.4  923.15  5025.0  923.65
  5038.8  929.63  5045.0  929.77  5059.6  933.61  5080.5  933.06  5095.2  930.74
  5124.6  932.90  5145.5  931.79  5160.2  932.73  5181.0  932.42  5252.2  936.50
  5260.7  938.05  5266.9  937.28  5281.6  939.49  5310.9  939.79  5460.6  949.07
#Mann=4,-1,0
  4516.3    0.05       0  4815.6    0.12       0  5006.9    0.07       0
  5025.0    0.12       0
Bank Sta=5006.9,5025
Exp/Cntr=0.3,0.1

Type RM Length L Ch R = 1,24500,500,500,500
BEGIN DESCRIPTION:
PECAN CREEK 49.0
END DESCRIPTION:
XS GIS Cut Line= 3
      2906055.67     10160653.12      2906404.58     10160277.45
      2906355.69     10160053.12
#Sta/Elev= 30
  4487.3  940.99  4508.6  939.69  4636.1  935.41  4734.8  933.74  4763.1  932.64
  4770.5  933.13  4848.2  931.27  4855.5  930.54  4862.3  930.91  4919.0  927.63
  4925.8  927.81  4968.4  922.46  4987.6  918.68  4988.1  918.18  5005.2  918.18
  5005.7  918.68  5013.9  920.08  5019.0  918.90  5024.9  920.68  5035.1  920.37
  5063.0  922.11  5068.1  921.80  5078.2  923.30  5106.8  927.92  5112.1  929.93
  5117.2  930.02  5127.3  931.78  5147.7  936.45  5210.2  940.83  5229.6  943.04
#Mann=4,-1,0
  4487.3    0.05       0  4987.6    0.05       0  5005.7    0.05       0
  5078.2    0.12       0
Bank Sta=4987.6,5005.7
Exp/Cntr=0.3,0.1

Type RM Length L Ch R = 1,24000,500,500,500
BEGIN DESCRIPTION:
PECAN CREEK 48.0
END DESCRIPTION:
XS GIS Cut Line= 3
      2906355.65     10160853.14      2906849.16     10160460.41
      2907039.96     10160252.90
#Sta/Elev= 30
  4369.3  941.87  4382.9  941.89  4419.8  939.94  4469.5  939.24  4497.1  937.81
  4511.1  938.37  4519.1  937.09  4533.5  936.33  4539.9  937.45  4583.2  934.14
  4740.0  931.35  4781.8  928.50  4853.9  925.71  4909.9  922.21  4931.7  922.32
  4938.8  922.03  4953.2  919.78  4959.6  917.71  4992.0  917.70  5007.8  917.55
  5008.3  917.05  5026.0  917.55  5031.0  920.29  5052.0  921.74  5069.9  923.96
  5087.8  925.25  5122.9  923.47  5143.5  923.38  5198.5  923.50  5281.9  924.15
#Mann=8,-1,0
  4369.3    0.05       0  4931.7    0.12       0  4992.0    0.05       0
  5007.8    0.03       0  5026.0    0.05       0  5069.9    0.12       0
  5143.5    0.05       0  5198.5    0.12       0
Bank Sta=5007.8,5026
Exp/Cntr=0.3,0.1

Type RM Length L Ch R = 1,23500,500,500,500
BEGIN DESCRIPTION:
PECAN CREEK 47.0
END DESCRIPTION:
XS GIS Cut Line= 3
      2906455.64     10160853.11      2907162.47     10160804.47
      2908105.67     10161303.11
#Sta/Elev= 30
  4291.5  939.38  4862.6  922.24  4919.5  920.55  4961.9  917.95  5003.9  917.58
  5020.8  914.42  5030.6  910.67  5049.3  910.04  5049.8  909.54  5071.1  910.04
  5082.8  912.95  5118.6  912.18  5134.9  915.38  5162.6  917.00  5276.7  919.29
  5297.7  918.63  5327.4  912.87  5349.4  915.66  5365.6  914.50  5399.5  919.41
  5491.5  923.88  5519.8  923.13  5591.8  929.58  5690.2  933.63  5704.9  935.81
  5794.6  938.09  5844.3  942.19  5919.9  944.94  5942.5  947.85  6066.9  953.36
#Mann=9,-1,0
  4291.5    0.05       0  4862.6    0.12       0  4919.5    0.05       0
  4961.9    0.12       0  5020.8    0.05       0  5049.3    0.07       0
  5071.1    0.05       0  5276.7    0.12       0  5491.5    0.05       0
Bank Sta=5049.3,5071.1
Exp/Cntr=0.3,0.1

Type RM Length L Ch R = 1,23000,495,495,495
BEGIN DESCRIPTION:
PECAN CREEK 46.0
END DESCRIPTION:
XS GIS Cut Line= 3
      2906705.67     10160953.10      2907181.33     10161289.16
      2907305.71     10161403.13
#Sta/Elev= 30
  4417.6  931.40  4496.4  928.25  4511.2  926.72  4576.5  923.88  4603.5  922.13
  4618.3  920.21  4639.2  919.43  4647.9  920.14  4689.7  919.09  4790.5  918.64
  4805.4  919.44  4912.5  917.65  4942.1  914.26  4948.2  912.56  4969.1  909.55
  5001.9  909.28  5002.4  908.78  5024.0  909.28  5041.3  909.86  5055.5  916.87
  5062.3  922.67  5069.7  925.17  5076.5  928.52  5090.7  932.14  5098.1  932.35
  5119.0  935.23  5126.4  935.41  5133.2  937.03  5156.5  939.22  5168.7  939.72
#Mann=5,-1,0
  4417.6    0.05       0  4790.5    0.12       0  5001.9    0.07       0
  5024.0    0.12       0  5156.5    0.05       0
Bank Sta=5001.9,5024
Exp/Cntr=0.3,0.1

Type RM Length L Ch R = 1,22505,314,314,314
BEGIN DESCRIPTION:
Mapping XS 0ae3157c
END DESCRIPTION:
XS GIS Cut Line= 2
      2906348.15     10161187.27      2907050.93     10161665.04
#Sta/Elev= 30
  4552.9  926.86  4591.1  925.60  4606.0  926.03  4648.0  923.62  4663.0  923.66
  4677.9  925.26  4698.9  924.66  4764.7  925.91  4779.6  924.79  4791.8  921.78
  4821.6  918.40  4864.3  917.20  4900.6  912.23  4914.4  905.32  4939.3  904.09
  4939.8  903.59  4961.4  904.09  4965.3  904.11  4980.2  909.34  5052.1  909.10
  5082.0  910.24  5094.1  912.17  5166.6  914.88  5282.6  922.68  5303.6  923.01
  5318.5  924.41  5348.0  924.46  5354.4  925.43  5360.5  924.85  5402.7  925.94
#Mann=3,-1,0
  4552.9    0.05       0  4939.3    0.03       0  4961.4    0.05       0
Bank Sta=4939.3,4961.4
Exp/Cntr=0.3,0.1