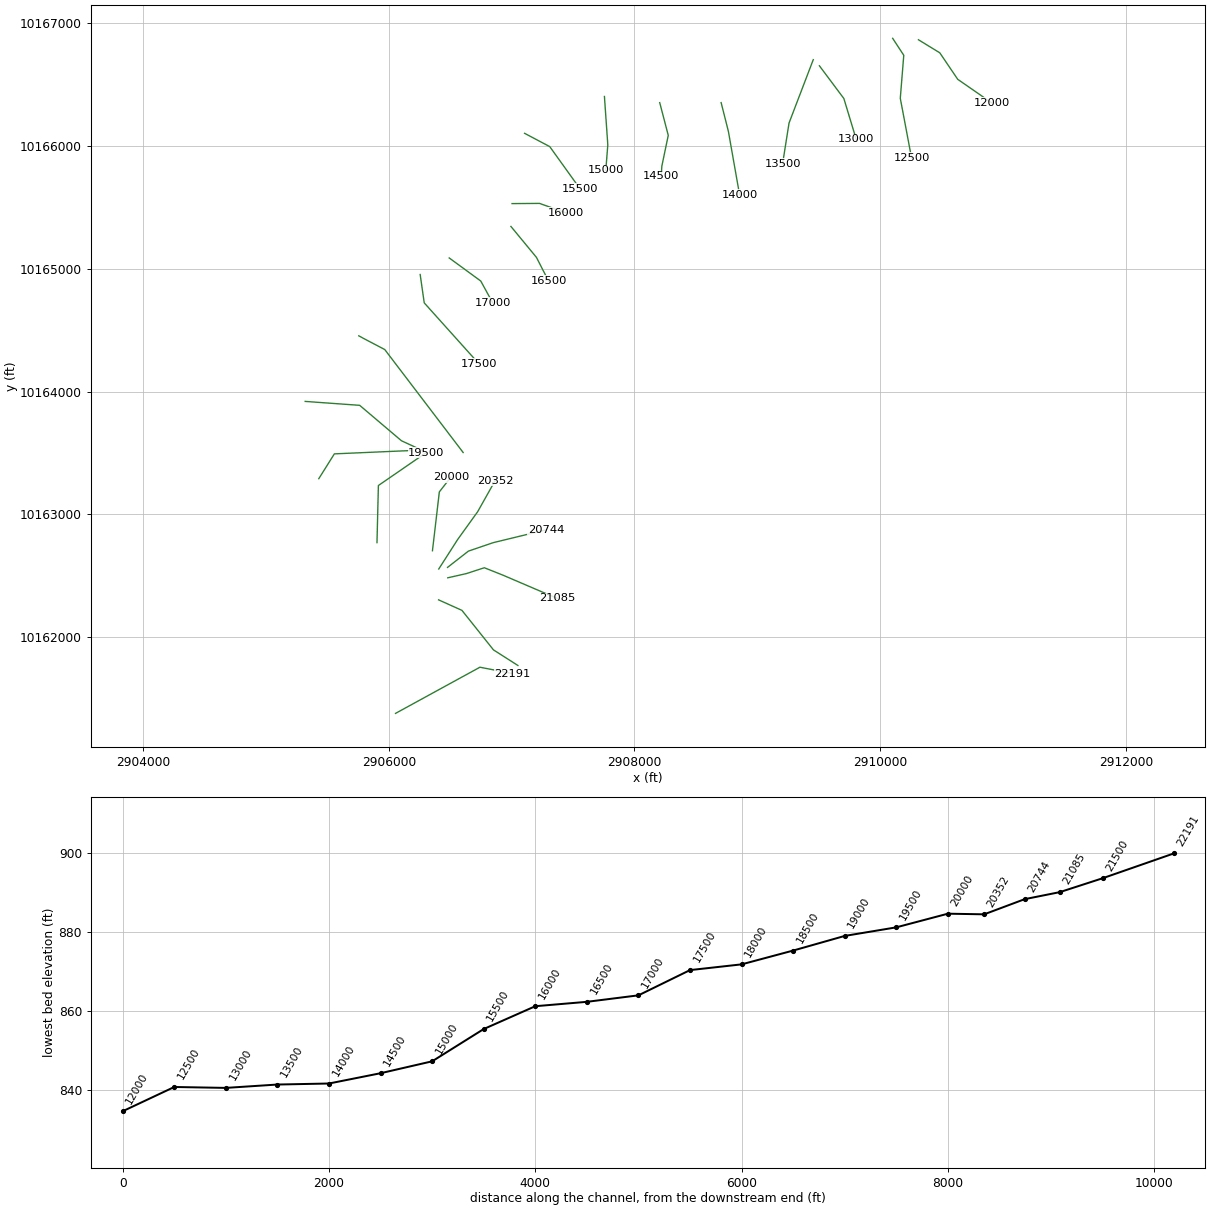
HEC-RAS study PECAN CREEK.prj: PECAN CREEK Base Level Engineering

--- PECAN CREEK.g01 (geometry) --- (continued)

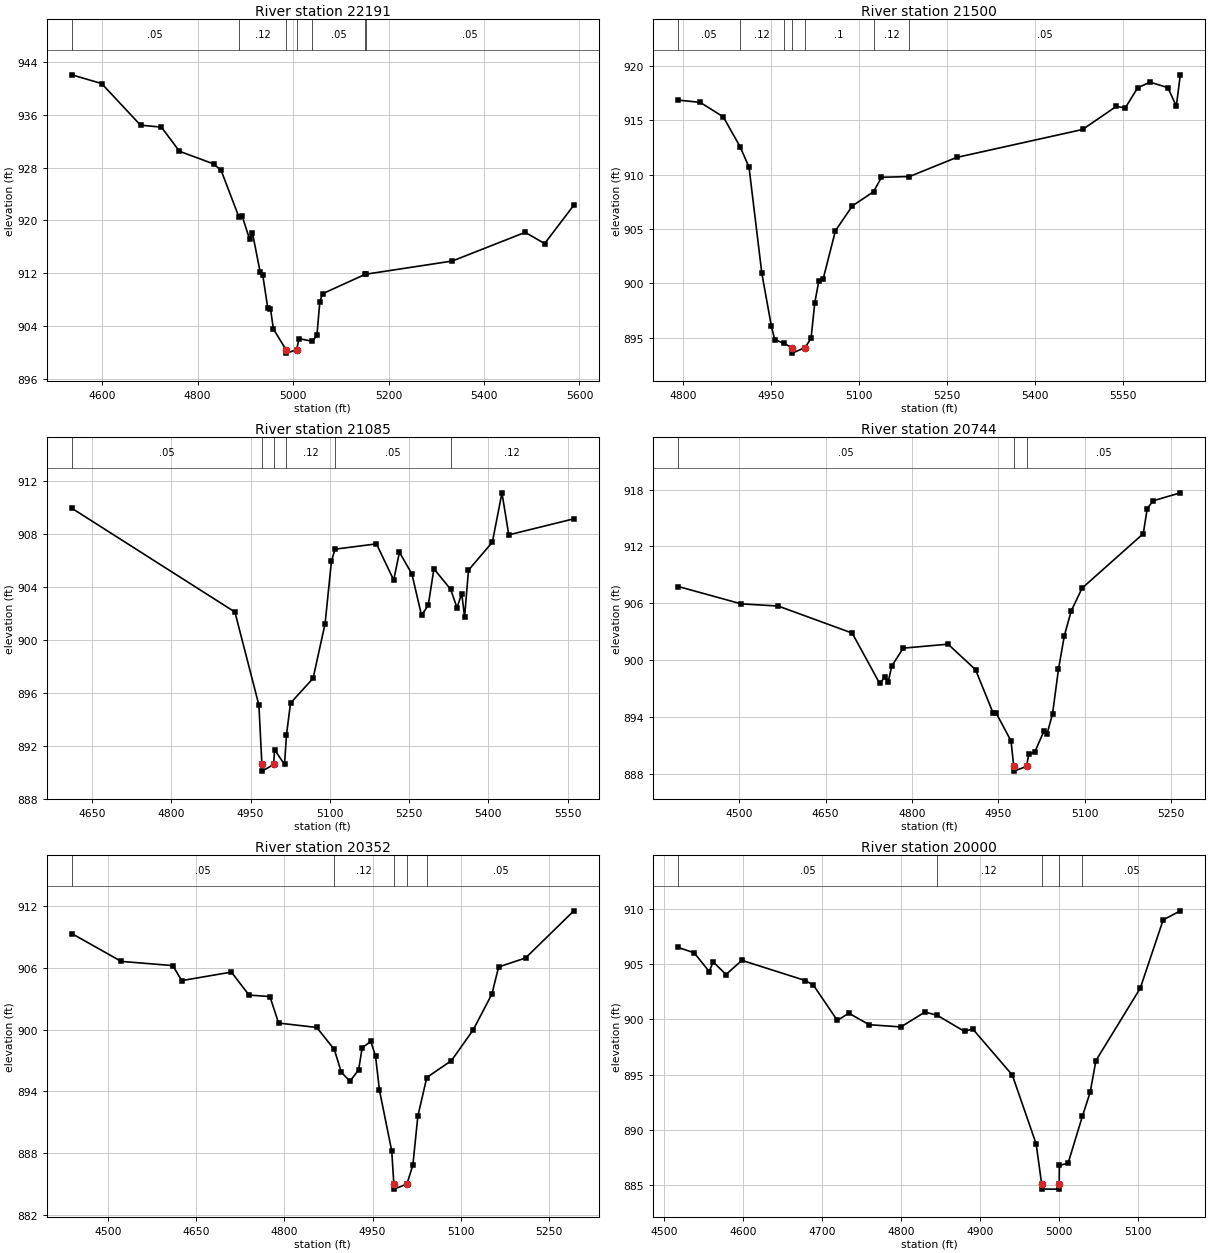
Type RM Length L Ch R = 1,22191,691,691,691
BEGIN DESCRIPTION:
Mapping XS 50fffaaf
END DESCRIPTION:
XS GIS Cut Line= 3
      2906055.24     10161378.47      2906742.18     10161754.45
      2907005.72     10161703.10
#Sta/Elev= 30
  4536.6  942.07  4599.1  940.75  4680.6  934.44  4724.3  934.14  4762.2  930.48
  4833.5  928.57  4849.4  927.58  4886.3  920.59  4893.1  920.74  4909.2  917.12
  4914.9  918.16  4931.0  912.24  4936.7  911.68  4947.1  906.72  4952.8  906.61
  4958.9  903.55  4985.4  900.38  4985.9  899.88  5007.5  900.38  5012.6  902.08
  5040.6  901.67  5050.1  902.60  5056.2  907.70  5061.9  908.89  5150.5  911.80
  5152.0  911.84  5333.5  913.84  5486.3  918.19  5527.0  916.49  5588.2  922.31
#Mann=7,-1,0
  4536.6    0.05       0  4886.3    0.12       0  4985.4    0.07       0
  5007.5    0.12       0  5040.6    0.05       0  5150.5    0.12       0
  5152.0    0.05       0
Bank Sta=4985.4,5007.5
Exp/Cntr=0.3,0.1

Type RM Length L Ch R = 1,21500,415,415,415
BEGIN DESCRIPTION:
PECAN CREEK 43.0
END DESCRIPTION:
XS GIS Cut Line= 4
      2906405.66     10162303.12      2906595.68     10162217.55
      2906852.21     10161895.68      2907051.40     10161768.54
#Sta/Elev= 30
  4791.6  916.84  4829.1  916.63  4868.4  915.30  4897.3  912.54  4912.3  910.68
  4934.2  900.92  4950.3  896.12  4956.1  894.84  4971.8  894.50  4985.5  894.10
  4986.0  893.60  5007.6  894.10  5018.1  894.95  5024.5  898.23  5031.2  900.18
  5038.9  900.44  5059.7  904.84  5088.5  907.12  5124.7  908.42  5138.2  909.75
  5186.0  909.82  5266.3  911.57  5481.2  914.14  5538.7  916.26  5554.0  916.12
  5575.1  917.96  5596.3  918.49  5626.7  917.98  5641.1  916.28  5647.9  919.16
#Mann=7,-1,0
  4791.6    0.05       0  4897.3    0.12       0  4971.8     0.1       0
  4985.5    0.07       0  5007.6     0.1       0  5124.7    0.12       0
  5186.0    0.05       0
Bank Sta=4985.5,5007.6
Exp/Cntr=0.3,0.1

Type RM Length L Ch R = 1,21085,341,341,341
BEGIN DESCRIPTION:
PECAN CREEK 42.0
END DESCRIPTION:
XS GIS Cut Line= 5
      2906480.74     10162482.85      2906632.74     10162517.28
      2906777.92     10162564.72      2906932.02     10162503.27
      2907368.83     10162315.85
#Sta/Elev= 30
  4611.8  909.92  4920.4  902.09  4965.8  895.07  4971.5  890.59  4972.0  890.09
  4993.6  890.59  4995.5  891.70  5014.3  890.59  5017.9  892.79  5025.6  895.22
  5068.3  897.09  5091.0  901.21  5103.0  905.91  5109.7  906.83  5188.2  907.23
  5220.8  904.50  5231.7  906.60  5255.2  904.96  5273.4  901.85  5286.1  902.59
  5296.9  905.35  5328.6  903.80  5340.5  902.42  5349.5  903.48  5354.9  901.72
  5362.3  905.25  5407.5  907.36  5425.6  911.08  5438.5  907.91  5561.6  909.12
#Mann=6,-1,0
  4611.8    0.05       0  4971.5    0.05       0  4993.6    0.05       0
  5017.9    0.12       0  5109.7    0.05       0  5328.6    0.12       0
Bank Sta=4971.5,4993.6
Exp/Cntr=0.3,0.1

Type RM Length L Ch R = 1,20744,392,392,392
BEGIN DESCRIPTION:
Mapping XS d194b152
END DESCRIPTION:
XS GIS Cut Line= 4
      2906478.56     10162567.49      2906648.47     10162700.17
      2906850.79     10162769.14      2907281.54     10162873.75
#Sta/Elev= 30
  4393.9  907.78  4503.4  905.95  4567.6  905.72  4696.2  902.87  4743.9  897.57
  4753.6  898.25  4758.9  897.74  4765.0  899.39  4785.0  901.28  4862.8  901.70
  4910.6  899.01  4941.2  894.43  4946.3  894.45  4972.3  891.49  4977.0  888.81
  4977.5  888.31  4999.2  888.81  5003.2  890.10  5013.5  890.32  5029.8  892.57
  5035.0  892.26  5044.4  894.34  5054.7  899.03  5064.9  902.58  5076.8  905.19
  5095.8  907.61  5202.1  913.35  5209.0  916.00  5219.3  916.82  5266.5  917.66
#Mann=3,-1,0
  4393.9    0.05       0  4977.0    0.05       0  4999.2    0.05       0
Bank Sta=4977,4999.2
Exp/Cntr=0.3,0.1

Type RM Length L Ch R = 1,20352,352,352,352
BEGIN DESCRIPTION:
Mapping XS 01a80278
END DESCRIPTION:
XS GIS Cut Line= 4
      2906406.97     10162554.50      2906561.26     10162795.18
      2906724.36     10163021.99      2906866.22     10163274.86
#Sta/Elev= 30
  4437.7  909.35  4521.9  906.64  4609.8  906.23  4625.0  904.77  4709.6  905.60
  4739.6  903.36  4775.2  903.22  4790.0  900.64  4855.0  900.21  4884.9  898.07
  4896.8  895.85  4911.5  894.98  4926.2  896.07  4932.4  898.24  4947.1  898.85
  4955.1  897.42  4961.8  894.10  4982.7  888.20  4986.3  884.98  4986.8  884.48
  5008.6  884.98  5018.7  886.82  5027.2  891.59  5042.4  895.34  5084.5  896.99
  5121.4  899.97  5153.3  903.46  5164.8  906.10  5210.6  906.97  5292.9  911.56
#Mann=5,-1,0
  4437.7    0.05       0  4884.9    0.12       0  4986.3    0.07       0
  5008.6    0.12       0  5042.4    0.05       0
Bank Sta=4986.3,5008.6
Exp/Cntr=0.3,0.1

Type RM Length L Ch R = 1,20000,500,500,500
BEGIN DESCRIPTION:
PECAN CREEK 40.0
END DESCRIPTION:
XS GIS Cut Line= 3
      2906355.68     10162703.07      2906411.66     10163182.31
      2906505.70     10163303.13
#Sta/Elev= 30
  4517.5  906.50  4537.7  906.01  4556.7  904.32  4561.7  905.19  4578.0  904.05
  4598.1  905.33  4678.6  903.50  4688.7  903.08  4718.9  899.90  4733.5  900.55
  4759.2  899.51  4799.4  899.31  4829.7  900.65  4845.2  900.37  4880.0  898.90
  4890.1  899.14  4940.4  894.96  4970.6  888.73  4977.5  885.14  4978.0  884.64
  4999.3  884.64  4999.8  885.14  5000.0  886.79  5011.0  886.98  5029.1  891.22
  5039.0  893.41  5046.3  896.27  5102.4  902.81  5131.4  908.99  5153.1  909.81
#Mann=5,-1,0
  4517.5    0.05       0  4845.2    0.12       0  4977.5    0.07       0
  4999.8    0.12       0  5029.1    0.05       0
Bank Sta=4977.5,4999.8
Exp/Cntr=0.3,0.1

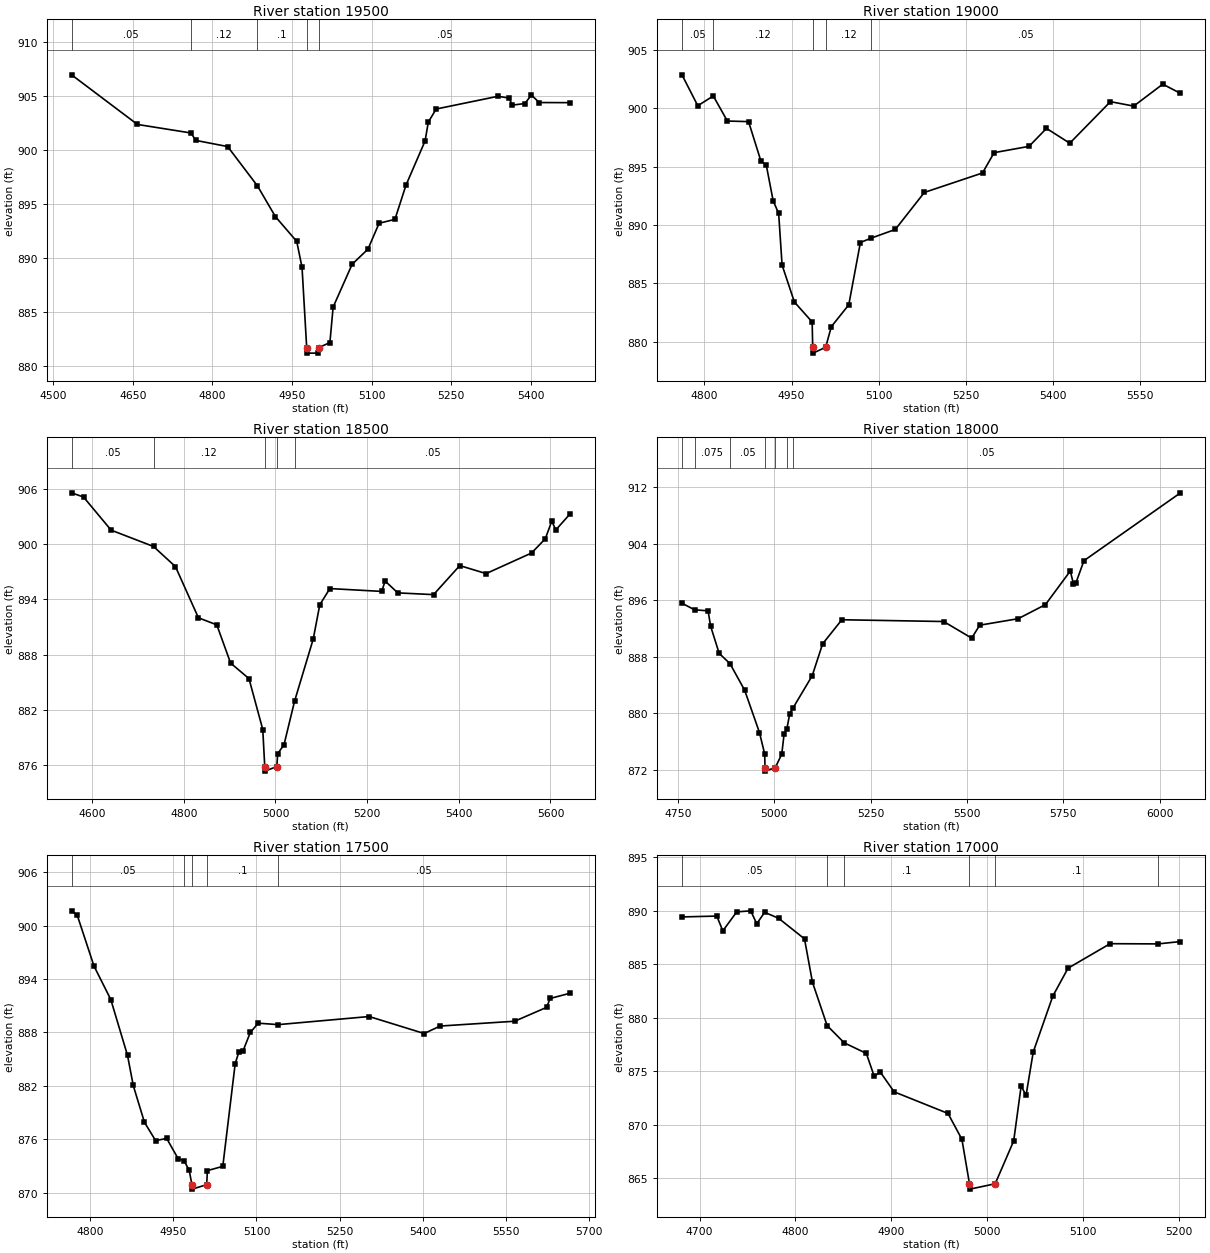
Type RM Length L Ch R = 1,19500,500,500,500
BEGIN DESCRIPTION:
PECAN CREEK 39.0
END DESCRIPTION:
XS GIS Cut Line= 3
      2905904.14     10162769.18      2905915.56     10163234.44
      2906305.69     10163503.12
#Sta/Elev= 30
  4534.6  906.99  4658.6  902.39  4759.4  901.60  4768.6  900.91  4828.6  900.34
  4884.8  896.69  4918.6  893.84  4958.7  891.55  4968.7  889.15  4977.5  881.69
  4978.0  881.19  4999.3  881.19  4999.8  881.69  5021.2  882.17  5027.3  885.46
  5063.1  889.43  5092.9  890.83  5113.9  893.23  5143.7  893.59  5164.6  896.77
  5200.5  900.86  5206.6  902.61  5221.4  903.82  5337.8  905.00  5358.7  904.84
  5364.8  904.18  5388.5  904.33  5400.8  905.12  5415.5  904.42  5473.7  904.41
#Mann=5,-1,0
  4534.6    0.05       0  4759.4    0.12       0  4884.8     0.1       0
  4977.5    0.05       0  4999.8    0.05       0
Bank Sta=4977.5,4999.8
Exp/Cntr=0.3,0.1

Type RM Length L Ch R = 1,19000,500,500,500
BEGIN DESCRIPTION:
PECAN CREEK 38.0
END DESCRIPTION:
XS GIS Cut Line= 3
      2905430.36     10163290.11      2905557.22     10163492.20
      2906176.13     10163519.10
#Sta/Elev= 30
  4761.4  902.87  4788.6  900.22  4815.3  901.06  4839.5  898.91  4876.0  898.86
  4897.2  895.49  4906.6  895.11  4918.4  892.06  4927.8  891.00  4933.7  886.57
  4954.9  883.40  4985.5  881.69  4986.4  879.52  4986.9  879.02  5008.7  879.52
  5018.5  881.29  5048.5  883.16  5068.5  888.50  5087.3  888.88  5128.6  889.62
  5178.6  892.79  5278.7  894.46  5298.7  896.20  5358.8  896.74  5388.8  898.28
  5428.9  897.01  5498.9  900.57  5539.0  900.19  5589.0  902.07  5619.5  901.28
#Mann=5,-1,0
  4761.4    0.05       0  4815.3    0.12       0  4986.4    0.07       0
  5008.7    0.12       0  5087.3    0.05       0
Bank Sta=4986.4,5008.7
Exp/Cntr=0.3,0.1

Type RM Length L Ch R = 1,18500,500,500,500
BEGIN DESCRIPTION:
PECAN CREEK 37.0
END DESCRIPTION:
XS GIS Cut Line= 4
      2905319.66     10163919.48      2905763.32     10163887.56
      2906103.56     10163598.81      2906282.00     10163516.41
#Sta/Elev= 30
  4555.2  905.61  4581.3  905.15  4641.4  901.55  4733.9  899.77  4781.8  897.58
  4831.9  892.01  4872.0  891.24  4902.1  887.08  4942.2  885.39  4972.3  879.85
  4976.6  875.82  4977.1  875.32  5003.0  875.82  5004.8  877.20  5018.7  878.21
  5041.7  882.94  5082.4  889.70  5096.7  893.43  5118.7  895.19  5231.8  894.88
  5239.2  896.01  5266.9  894.72  5344.9  894.53  5402.1  897.69  5459.6  896.82
  5558.7  899.06  5588.7  900.61  5602.8  902.53  5611.6  901.57  5642.8  903.32
#Mann=5,-1,0
  4555.2    0.05       0  4733.9    0.12       0  4976.6    0.07       0
  5003.0    0.12       0  5041.7    0.05       0
Bank Sta=4976.6,5003
Exp/Cntr=0.3,0.1

Type RM Length L Ch R = 1,18000,500,500,500
BEGIN DESCRIPTION:
PECAN CREEK 36.0
END DESCRIPTION:
XS GIS Cut Line= 4
      2905756.09     10164453.82      2905796.26     10164431.80
      2905967.38     10164341.91      2906605.65     10163503.15
#Sta/Elev= 30
  4760.9  895.59  4793.4  894.66  4828.6  894.51  4835.2  892.34  4857.3  888.50
  4885.5  887.03  4923.4  883.29  4961.9  877.29  4975.5  874.23  4976.2  872.33
  4976.7  871.83  5002.9  872.33  5019.7  874.23  5025.9  877.13  5032.7  877.73
  5040.5  879.98  5049.6  880.83  5098.6  885.32  5125.7  889.84  5175.6  893.25
  5439.7  893.00  5512.4  890.65  5533.2  892.48  5633.0  893.40  5703.7  895.39
  5768.2  900.15  5776.4  898.29  5782.7  898.46  5803.6  901.61  6054.0  911.21
#Mann=7,-1,0
  4760.9    0.05       0  4793.4   0.075       0  4885.5    0.05       0
  4976.2    0.05       0  5002.9    0.05       0  5032.7    0.12       0
  5049.6    0.05       0
Bank Sta=4976.2,5002.9
Exp/Cntr=0.3,0.1

Type RM Length L Ch R = 1,17500,500,500,500
BEGIN DESCRIPTION:
PECAN CREEK 35.0
END DESCRIPTION:
XS GIS Cut Line= 3
      2906255.68     10164953.14      2906288.80     10164722.11
      2906733.40     10164226.64
#Sta/Elev= 30
  4766.6  901.66  4776.7  901.18  4807.0  895.45  4837.3  891.69  4867.5  885.40
  4877.8  882.03  4898.0  877.89  4918.2  875.83  4938.1  876.08  4958.6  873.82
  4969.5  873.56  4978.8  872.48  4983.6  870.88  4984.1  870.38  5010.3  870.88
  5011.5  872.46  5039.3  872.94  5061.7  884.50  5068.1  885.75  5075.7  885.90
  5088.9  887.99  5103.3  889.03  5139.4  888.87  5303.3  889.78  5402.5  887.87
  5431.3  888.71  5565.7  889.25  5623.3  890.81  5629.7  891.81  5665.7  892.40
#Mann=5,-1,0
  4766.6    0.05       0  4969.5     0.1       0  4983.6    0.07       0
  5010.3     0.1       0  5139.4    0.05       0
Bank Sta=4983.6,5010.3
Exp/Cntr=0.3,0.1

Type RM Length L Ch R = 1,17000,500,500,500
BEGIN DESCRIPTION:
PECAN CREEK 34.0
END DESCRIPTION:
XS GIS Cut Line= 3
      2906491.96     10165088.07      2906748.85     10164900.12
      2906845.77     10164723.24
#Sta/Elev= 30
  4681.7  889.43  4718.0  889.51  4724.3  888.13  4738.8  889.90  4753.4  890.00
  4759.7  888.79  4767.9  889.86  4782.4  889.31  4809.5  887.38  4817.8  883.33
  4833.1  879.28  4850.9  877.67  4874.0  876.68  4882.2  874.55  4888.5  874.94
  4903.0  873.09  4959.2  871.07  4973.7  868.65  4981.6  864.50  4982.1  864.00
  5008.4  864.50  5027.7  868.50  5035.5  873.64  5040.6  872.75  5048.1  876.81
  5068.6  882.05  5084.4  884.64  5128.3  886.93  5178.3  886.91  5201.7  887.13
#Mann=6,-1,0
  4681.7    0.05       0  4833.1    0.12       0  4850.9     0.1       0
  4981.6    0.07       0  5008.4     0.1       0  5178.3    0.05       0
Bank Sta=4981.6,5008.4
Exp/Cntr=0.3,0.1

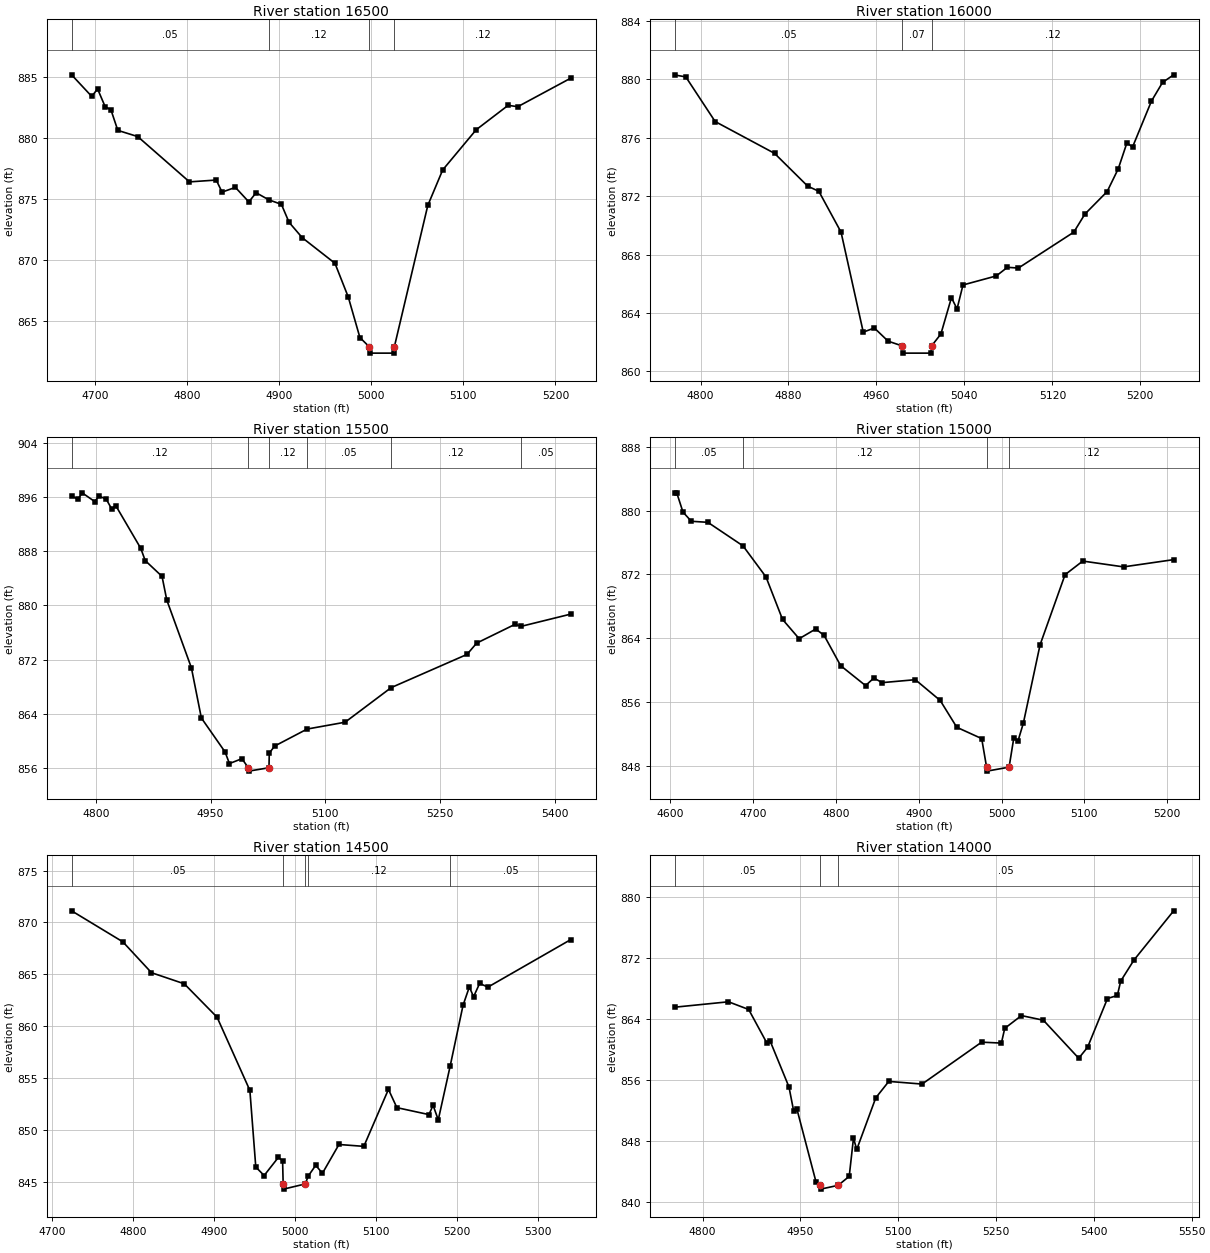
Type RM Length L Ch R = 1,16500,500,500,500
BEGIN DESCRIPTION:
PECAN CREEK 33.0
END DESCRIPTION:
XS GIS Cut Line= 3
      2906994.66     10165344.47      2907201.93     10165093.11
      2907300.76     10164900.48
#Sta/Elev= 30
  4674.2  885.16  4696.1  883.39  4702.4  884.01  4710.7  882.54  4716.9  882.30
  4724.4  880.61  4746.1  880.10  4802.3  876.39  4831.4  876.54  4837.7  875.55
  4852.2  875.94  4866.8  874.75  4874.7  875.50  4888.5  874.92  4902.2  874.55
  4910.5  873.08  4924.8  871.82  4960.4  869.72  4974.9  866.95  4987.5  863.64
  4997.9  862.86  4998.4  862.36  5024.4  862.36  5024.9  862.86  5061.3  874.46
  5077.5  877.37  5113.9  880.66  5148.6  882.66  5159.1  882.55  5216.5  884.88
#Mann=4,-1,0
  4674.2    0.05       0  4888.5    0.12       0  4997.9    0.07       0
  5024.9    0.12       0
Bank Sta=4997.9,5024.9
Exp/Cntr=0.3,0.1

Type RM Length L Ch R = 1,16000,500,500,500
BEGIN DESCRIPTION:
PECAN CREEK 32.0
END DESCRIPTION:
XS GIS Cut Line= 3
      2907003.77     10165530.70      2907227.27     10165532.27
      2907444.28     10165455.17
#Sta/Elev= 30
  4776.5  880.31  4786.6  880.18  4813.3  877.12  4867.3  874.94  4897.5  872.69
  4907.6  872.34  4927.8  869.54  4948.0  862.69  4958.1  862.97  4970.6  862.07
  4983.2  861.75  4983.7  861.25  5009.7  861.25  5010.2  861.75  5018.6  862.56
  5028.2  865.05  5033.3  864.28  5038.7  865.92  5069.0  866.54  5079.1  867.13
  5089.1  867.08  5139.5  869.54  5149.6  870.78  5169.8  872.32  5179.9  873.88
  5187.8  875.66  5192.9  875.37  5210.1  878.52  5220.2  879.80  5230.3  880.32
#Mann=3,-1,0
  4776.5    0.05       0  4983.2    0.07       0  5010.2    0.12       0
Bank Sta=4983.2,5010.2
Exp/Cntr=0.3,0.1

Type RM Length L Ch R = 1,15500,500,500,500
BEGIN DESCRIPTION:
PECAN CREEK 31.0
END DESCRIPTION:
XS GIS Cut Line= 3
      2907105.71     10166103.10      2907310.49     10165994.91
      2907555.71     10165653.07
#Sta/Elev= 30
  4768.4  896.25  4776.6  895.70  4782.2  896.68  4798.6  895.39  4804.2  896.20
  4813.6  895.75  4820.6  894.33  4826.2  894.77  4858.8  888.46  4864.6  886.65
  4886.6  884.31  4892.8  880.81  4925.0  870.77  4938.0  863.35  4969.0  858.32
  4974.7  856.60  4991.0  857.32  4999.4  855.98  4999.9  855.48  5026.4  855.98
  5026.8  858.14  5033.8  859.19  5076.3  861.71  5125.9  862.72  5186.1  867.84
  5285.3  872.76  5297.9  874.43  5348.2  877.22  5355.9  876.91  5420.7  878.72
#Mann=6,-1,0
  4768.4    0.12       0  4999.4    0.07       0  5026.4    0.12       0
  5076.3    0.05       0  5186.1    0.12       0  5355.9    0.05       0
Bank Sta=4999.4,5026.4
Exp/Cntr=0.3,0.1

Type RM Length L Ch R = 1,15000,500,500,500
BEGIN DESCRIPTION:
PECAN CREEK 30.0
END DESCRIPTION:
XS GIS Cut Line= 3
      2907755.68     10166403.13      2907783.13     10166009.19
      2907766.75     10165801.93
#Sta/Elev= 30
  4605.1  882.23  4607.6  882.23  4615.1  879.82  4625.2  878.66  4645.2  878.53
  4687.7  875.57  4715.4  871.68  4735.4  866.35  4755.5  863.93  4775.5  865.15
  4785.6  864.35  4805.6  860.55  4835.7  858.05  4845.7  859.00  4855.7  858.42
  4895.8  858.79  4925.9  856.18  4945.9  852.82  4976.0  851.40  4981.9  847.82
  4982.4  847.32  5009.1  847.82  5014.8  851.50  5019.9  851.12  5026.3  853.33
  5046.5  863.16  5076.7  871.96  5098.1  873.67  5147.4  872.94  5207.9  873.85
#Mann=4,-1,0
  4605.1    0.05       0  4687.7    0.12       0  4981.9    0.07       0
  5009.1    0.12       0
Bank Sta=4981.9,5009.1
Exp/Cntr=0.3,0.1

Type RM Length L Ch R = 1,14500,500,500,500
BEGIN DESCRIPTION:
PECAN CREEK 29.0
END DESCRIPTION:
XS GIS Cut Line= 4
      2908205.68     10166353.14      2908275.28     10166086.37
      2908223.24     10165837.19      2908217.46     10165751.54
#Sta/Elev= 30
  4724.3  871.12  4787.6  868.13  4822.9  865.16  4863.4  864.09  4903.9  860.87
  4944.4  853.82  4951.7  846.44  4962.0  845.62  4979.7  847.38  4984.8  847.03
  4985.5  844.81  4986.0  844.31  5012.8  844.81  5016.5  845.58  5025.7  846.60
  5034.0  845.84  5054.4  848.61  5085.1  848.43  5115.5  853.92  5125.9  852.16
  5165.5  851.49  5170.6  852.39  5177.0  850.98  5191.6  856.13  5207.6  862.02
  5215.4  863.79  5220.6  862.84  5228.1  864.13  5238.3  863.77  5340.4  868.34
#Mann=5,-1,0
  4724.3    0.05       0  4985.5    0.05       0  5012.8    0.05       0
  5016.5    0.12       0  5191.6    0.05       0
Bank Sta=4985.5,5012.8
Exp/Cntr=0.3,0.1

Type RM Length L Ch R = 1,14000,500,500,500
BEGIN DESCRIPTION:
PECAN CREEK 28.0
END DESCRIPTION:
XS GIS Cut Line= 3
      2908705.68     10166353.13      2908765.01     10166117.58
      2908855.68     10165603.11
#Sta/Elev= 30
  4757.1  865.59  4839.6  866.30  4870.6  865.29  4898.4  860.90  4903.5  861.15
  4932.4  855.12  4939.5  852.00  4944.6  852.21  4973.7  842.71  4980.6  842.21
  4981.1  841.71  5007.9  842.21  5024.8  843.39  5031.3  848.38  5036.4  846.93
  5065.5  853.69  5085.5  855.85  5136.5  855.50  5227.9  861.00  5258.2  860.88
  5263.3  862.81  5288.9  864.49  5322.6  863.88  5376.8  858.89  5390.4  860.33
  5420.9  866.73  5436.0  867.13  5441.2  869.02  5461.5  871.78  5522.4  878.24
#Mann=3,-1,0
  4757.1    0.05       0  4980.6    0.03       0  5007.9    0.05       0
Bank Sta=4980.6,5007.9
Exp/Cntr=0.3,0.1

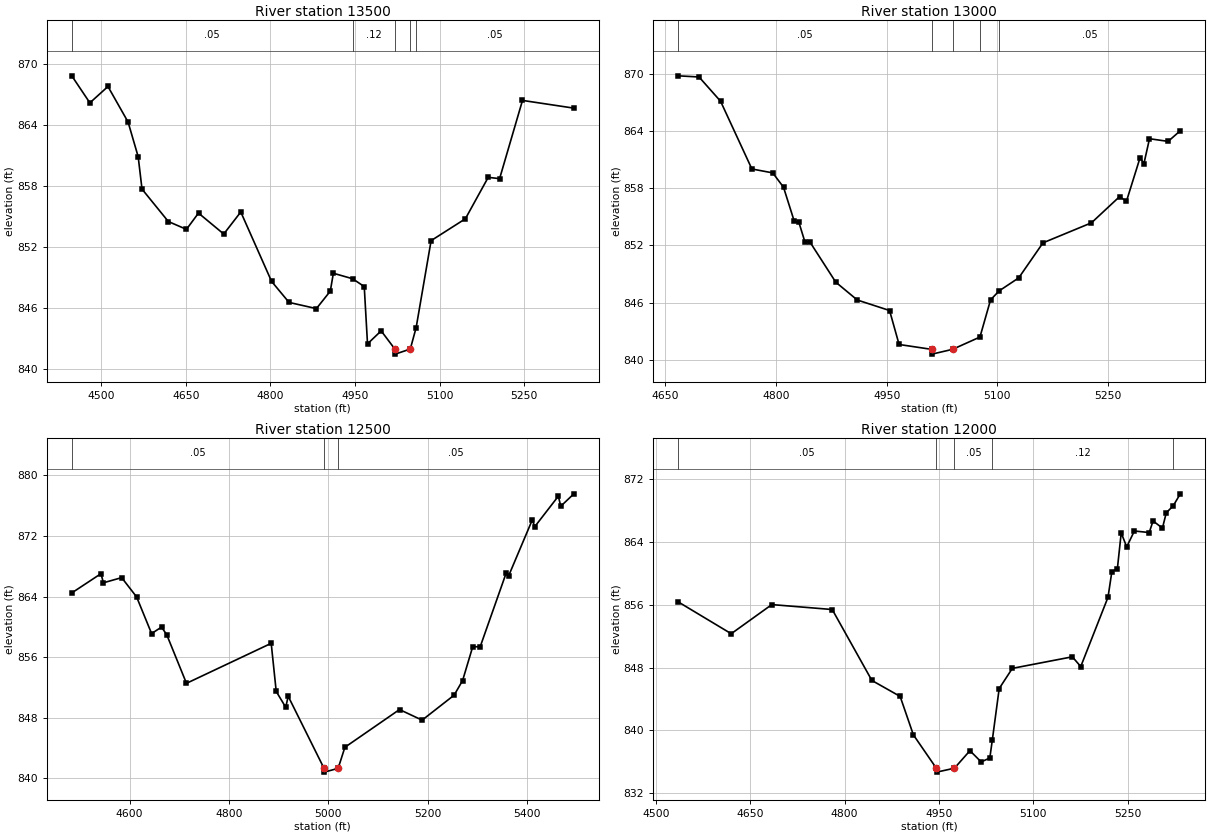
Type RM Length L Ch R = 1,13500,500,500,500
BEGIN DESCRIPTION:
PECAN CREEK 27.0
END DESCRIPTION:
XS GIS Cut Line= 3
      2909455.69     10166703.12      2909258.49     10166187.01
      2909205.68     10165853.06
#Sta/Elev= 30
  4447.5  868.84  4479.6  866.18  4511.7  867.79  4547.4  864.29  4565.3  860.88
  4572.1  857.69  4618.8  854.50  4650.9  853.73  4672.3  855.33  4717.1  853.27
  4747.3  855.44  4801.9  848.61  4832.9  846.54  4881.4  845.93  4906.1  847.65
  4911.5  849.41  4945.6  848.87  4966.3  848.10  4972.1  842.46  4996.3  843.74
  5020.6  841.95  5021.1  841.45  5048.0  841.95  5058.4  844.07  5084.9  852.62
  5145.7  854.77  5186.2  858.85  5206.4  858.72  5247.0  866.42  5338.1  865.66
#Mann=5,-1,0
  4447.5    0.05       0  4945.6    0.12       0  5020.6    0.07       0
  5048.0    0.12       0  5058.4    0.05       0
Bank Sta=5020.6,5048
Exp/Cntr=0.3,0.1

Type RM Length L Ch R = 1,13000,500,500,500
BEGIN DESCRIPTION:
PECAN CREEK 26.0
END DESCRIPTION:
XS GIS Cut Line= 3
      2909505.66     10166653.14      2909704.71     10166386.56
      2909805.68     10166053.11
#Sta/Elev= 30
  4667.3  869.76  4695.5  869.64  4724.7  867.10  4767.2  860.00  4795.5  859.59
  4810.1  858.09  4824.7  854.52  4831.0  854.40  4839.3  852.32  4845.6  852.39
  4881.0  848.14  4910.2  846.27  4954.0  845.17  4966.9  841.61  5011.0  841.10
  5011.5  840.60  5039.4  841.10  5076.6  842.39  5091.0  846.29  5102.7  847.23
  5129.2  848.59  5162.1  852.26  5227.9  854.36  5266.1  857.11  5275.3  856.61
  5293.8  861.18  5299.0  860.55  5306.6  863.17  5331.9  862.89  5348.4  864.01
#Mann=5,-1,0
  4667.3    0.05       0  5011.0    0.03       0  5039.4    0.05       0
  5076.6    0.12       0  5102.7    0.05       0
Bank Sta=5011,5039.4
Exp/Cntr=0.3,0.1

Type RM Length L Ch R = 1,12500,500,500,500
BEGIN DESCRIPTION:
PECAN CREEK 25.0
END DESCRIPTION:
XS GIS Cut Line= 4
      2910102.11     10166876.80      2910192.39     10166738.66
      2910164.09     10166388.43      2910255.69     10165903.10
#Sta/Elev= 30
  4483.6  864.48  4542.3  867.02  4547.3  865.82  4584.0  866.50  4614.1  863.95
  4644.2  859.12  4664.2  859.97  4674.6  858.98  4714.4  852.55  4884.9  857.83
  4895.0  851.48  4914.1  849.39  4919.1  850.84  4991.2  841.33  4991.7  840.83
  5019.6  841.33  5033.2  844.11  5143.1  849.09  5188.6  847.69  5253.0  850.99
  5270.0  852.91  5290.4  857.38  5305.4  857.37  5357.8  867.12  5362.9  866.77
  5410.2  874.11  5415.3  873.23  5462.6  877.24  5467.7  875.93  5493.9  877.56
#Mann=3,-1,0
  4483.6    0.05       0  4991.2    0.03       0  5019.6    0.05       0
Bank Sta=4991.2,5019.6
Exp/Cntr=0.3,0.1

Type RM Length L Ch R = 1,12000,500,500,500
BEGIN DESCRIPTION:
PECAN CREEK 24.0
END DESCRIPTION:
XS GIS Cut Line= 4
      2910311.84     10166865.24      2910485.60     10166758.90
      2910631.68     10166543.00      2910905.71     10166353.09
#Sta/Elev= 30
  4535.6  856.37  4619.8  852.32  4684.3  856.03  4780.3  855.40  4843.3  846.37
  4888.2  844.34  4909.2  839.45  4945.7  835.20  4946.2  834.70  4974.5  835.20
  4999.1  837.43  5017.0  836.00  5030.7  836.50  5034.7  838.80  5045.6  845.34
  5066.5  847.91  5161.8  849.38  5175.2  848.14  5218.5  856.96  5224.6  860.21
  5233.4  860.60  5239.5  865.16  5248.2  863.37  5260.4  865.40  5284.0  865.20
  5290.1  866.68  5305.0  865.76  5311.1  867.72  5322.1  868.60  5333.4  870.13
#Mann=5,-1,0
  4535.6    0.05       0  4945.7    0.05       0  4974.5    0.05       0
  5034.7    0.12       0  5322.1    0.05       0
Bank Sta=4945.7,4974.5
Exp/Cntr=0.3,0.1