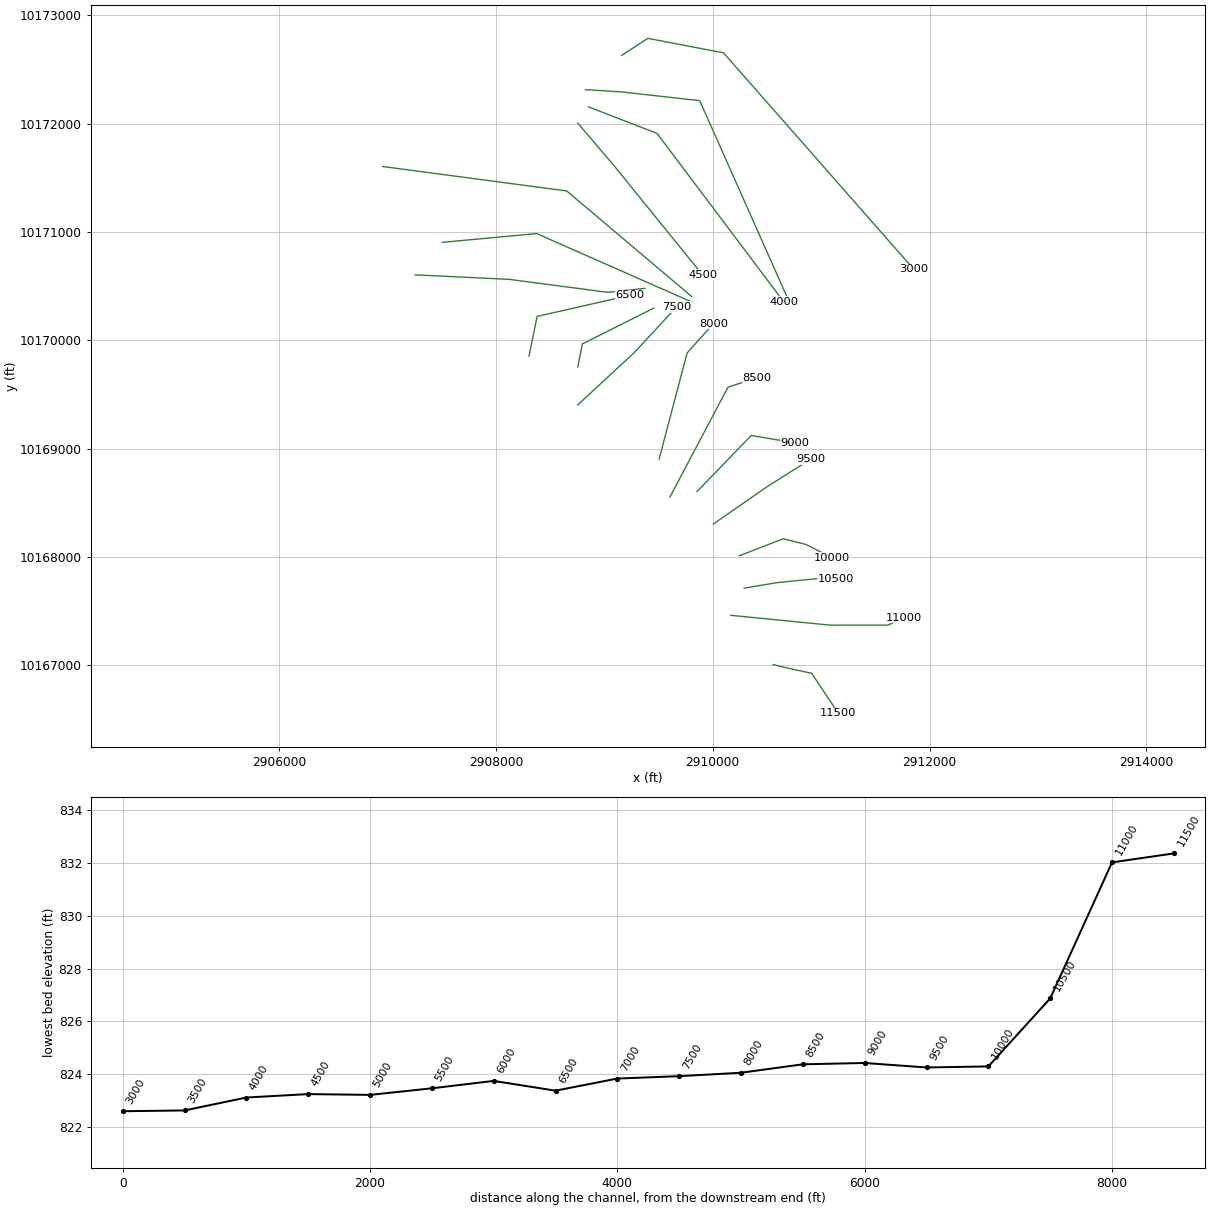
HEC-RAS study PECAN CREEK.prj: PECAN CREEK Base Level Engineering

--- PECAN CREEK.g01 (geometry) --- (continued)

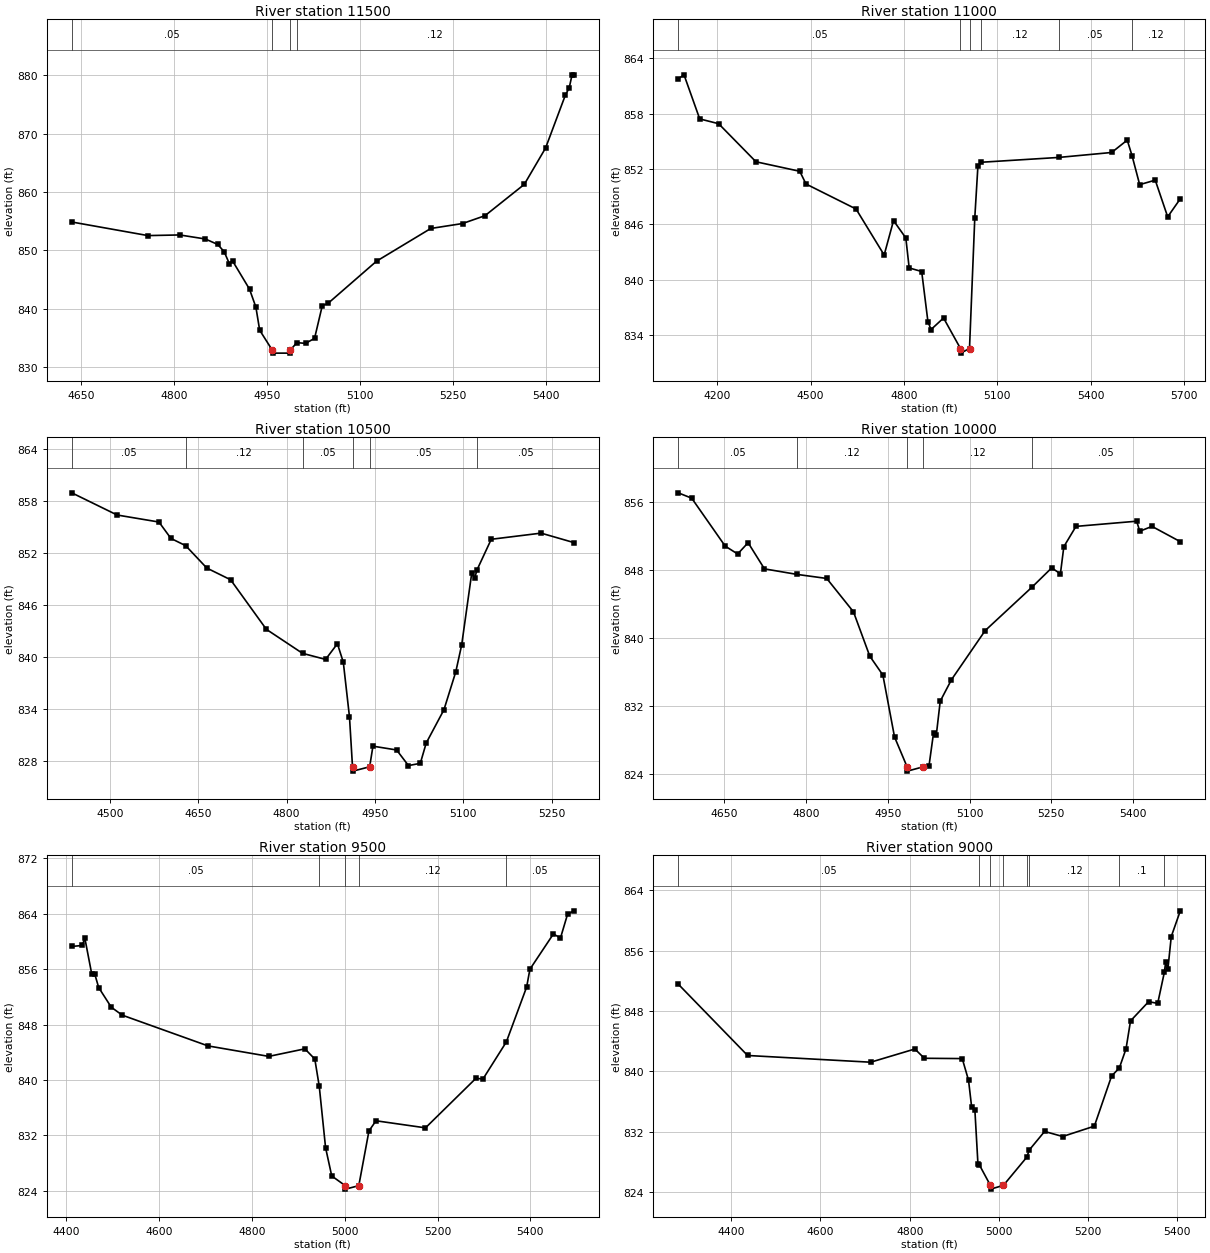
Type RM Length L Ch R = 1,11500,500,500,500
BEGIN DESCRIPTION:
PECAN CREEK 23.0
END DESCRIPTION:
XS GIS Cut Line= 4
      2910556.35     10167005.99      2910669.76     10166978.15
      2910912.54     10166925.03      2911159.05     10166555.39
#Sta/Elev= 30
  4634.7  854.85  4757.5  852.52  4808.7  852.63  4850.0  851.94  4870.1  851.00
  4880.4  849.76  4888.8  847.71  4893.9  848.19  4921.3  843.34  4931.6  840.25
  4937.7  836.30  4958.1  832.87  4958.6  832.37  4986.4  832.37  4986.9  832.87
  4997.7  834.17  5011.6  834.04  5026.2  834.90  5038.6  840.49  5047.8  840.89
  5126.1  848.13  5213.6  853.74  5264.9  854.59  5301.0  855.93  5364.4  861.30
  5398.7  867.53  5430.8  876.65  5436.8  877.83  5441.4  880.08  5444.3  880.08
#Mann=4,-1,0
  4634.7    0.05       0  4958.1    0.07       0  4986.9    0.05       0
  4997.7    0.12       0
Bank Sta=4958.1,4986.9
Exp/Cntr=0.3,0.1

Type RM Length L Ch R = 1,11000,500,500,500
BEGIN DESCRIPTION:
PECAN CREEK 22.0
END DESCRIPTION:
XS GIS Cut Line= 4
      2910167.00     10167460.42      2911087.72     10167369.51
      2911618.76     10167370.03      2911759.89     10167440.07
#Sta/Elev= 30
  4074.8  861.78  4093.4  862.21  4143.8  857.43  4204.6  856.91  4324.7  852.78
  4465.4  851.75  4485.5  850.37  4646.3  847.66  4736.7  842.67  4766.8  846.40
  4806.3  844.52  4817.1  841.27  4857.3  840.88  4877.4  835.44  4887.4  834.59
  4927.6  835.84  4982.0  832.53  4982.5  832.03  5011.0  832.53  5028.0  846.71
  5038.0  852.29  5049.1  852.73  5297.2  853.25  5468.0  853.79  5518.0  855.13
  5533.3  853.46  5558.0  850.30  5608.0  850.79  5648.0  846.81  5688.6  848.77
#Mann=6,-1,0
  4074.8    0.05       0  4982.0    0.05       0  5011.0    0.05       0
  5049.1    0.12       0  5297.2    0.05       0  5533.3    0.12       0
Bank Sta=4982,5011
Exp/Cntr=0.3,0.1

Type RM Length L Ch R = 1,10500,500,500,500
BEGIN DESCRIPTION:
PECAN CREEK 21.0
END DESCRIPTION:
XS GIS Cut Line= 5
      2910289.73     10167711.30      2910596.17     10167762.32
      2910848.91     10167788.02      2911062.32     10167806.65
      2911134.76     10167795.58
#Sta/Elev= 30
  4435.3  858.98  4512.3  856.42  4583.3  855.61  4603.6  853.72  4628.7  852.88
  4664.5  850.30  4704.9  848.95  4765.6  843.23  4827.0  840.46  4866.1  839.76
  4886.2  841.57  4896.2  839.43  4906.7  833.11  4911.8  827.37  4912.3  826.87
  4940.9  827.37  4946.5  829.75  4986.7  829.31  5006.8  827.51  5026.9  827.77
  5036.9  830.11  5067.0  833.95  5087.1  838.33  5097.1  841.43  5114.1  849.68
  5119.1  849.14  5123.3  850.11  5147.3  853.62  5231.9  854.33  5287.5  853.24
#Mann=6,-1,0
  4435.3    0.05       0  4628.7    0.12       0  4827.0    0.05       0
  4911.8    0.07       0  4940.9    0.05       0  5123.3    0.05       0
Bank Sta=4911.8,4940.9
Exp/Cntr=0.3,0.1

Type RM Length L Ch R = 1,10000,500,500,500
BEGIN DESCRIPTION:
PECAN CREEK 20.0
END DESCRIPTION:
XS GIS Cut Line= 4
      2910245.28     10168010.12      2910650.84     10168167.13
      2910859.45     10168114.73      2911102.07     10167991.75
#Sta/Elev= 30
  4565.1  857.05  4589.8  856.42  4651.3  850.78  4674.2  849.85  4693.4  851.18
  4723.4  848.10  4782.9  847.45  4837.8  846.97  4886.9  843.04  4916.8  837.83
  4940.9  835.60  4962.3  828.31  4985.4  824.79  4985.9  824.29  5014.5  824.79
  5025.6  824.91  5033.9  828.77  5039.1  828.59  5046.2  832.52  5066.9  835.06
  5128.7  840.83  5215.1  845.97  5251.0  848.22  5266.9  847.51  5273.2  850.71
  5295.5  853.10  5406.9  853.71  5412.7  852.53  5435.1  853.10  5487.1  851.30
#Mann=5,-1,0
  4565.1    0.05       0  4782.9    0.12       0  4985.4    0.07       0
  5014.5    0.12       0  5215.1    0.05       0
Bank Sta=4985.4,5014.5
Exp/Cntr=0.3,0.1

Type RM Length L Ch R = 1,9500,500,500,500
BEGIN DESCRIPTION:
PECAN CREEK 19.0
END DESCRIPTION:
XS GIS Cut Line= 3
      2910005.72     10168303.14      2910488.75     10168638.97
      2910905.71     10168903.13
#Sta/Elev= 30
  4411.7  859.26  4433.9  859.40  4440.0  860.41  4454.9  855.22  4461.0  855.33
  4469.7  853.33  4496.9  850.49  4520.4  849.35  4705.4  844.91  4836.3  843.40
  4914.0  844.49  4935.4  843.02  4945.0  839.08  4958.6  830.23  4971.9  826.15
  5001.0  824.75  5001.5  824.25  5030.2  824.75  5052.1  832.65  5067.3  834.11
  5173.9  833.09  5282.5  840.23  5297.8  840.14  5348.1  845.48  5391.9  853.41
  5398.9  855.97  5449.5  861.06  5464.8  860.48  5480.0  863.90  5493.6  864.40
#Mann=5,-1,0
  4411.7    0.05       0  4945.0    0.12       0  5001.0    0.07       0
  5030.2    0.12       0  5348.1    0.05       0
Bank Sta=5001,5030.2
Exp/Cntr=0.3,0.1

Type RM Length L Ch R = 1,9000,500,500,500
BEGIN DESCRIPTION:
PECAN CREEK 18.0
END DESCRIPTION:
XS GIS Cut Line= 3
      2909855.67     10168603.10      2910354.73     10169120.40
      2910755.73     10169053.10
#Sta/Elev= 30
  4281.2  851.57  4436.7  842.12  4712.5  841.23  4811.6  842.98  4832.9  841.75
  4917.8  841.71  4931.9  838.84  4938.9  835.28  4946.1  834.92  4953.0  827.74
  4956.1  827.64  4980.9  824.92  4981.4  824.42  5010.1  824.92  5062.2  828.63
  5068.3  829.62  5102.4  832.06  5142.9  831.39  5213.9  832.76  5252.5  839.39
  5270.0  840.48  5284.9  843.00  5295.0  846.70  5335.6  849.25  5355.9  849.02
  5370.8  853.13  5373.7  854.46  5378.8  853.60  5386.3  857.87  5406.6  861.28
#Mann=8,-1,0
  4281.2    0.05       0  4956.1     0.1       0  4980.9    0.03       0
  5010.1     0.1       0  5062.2     0.1       0  5068.3    0.12       0
  5270.0     0.1       0  5370.8    0.05       0
Bank Sta=4980.9,5010.1
Exp/Cntr=0.3,0.1

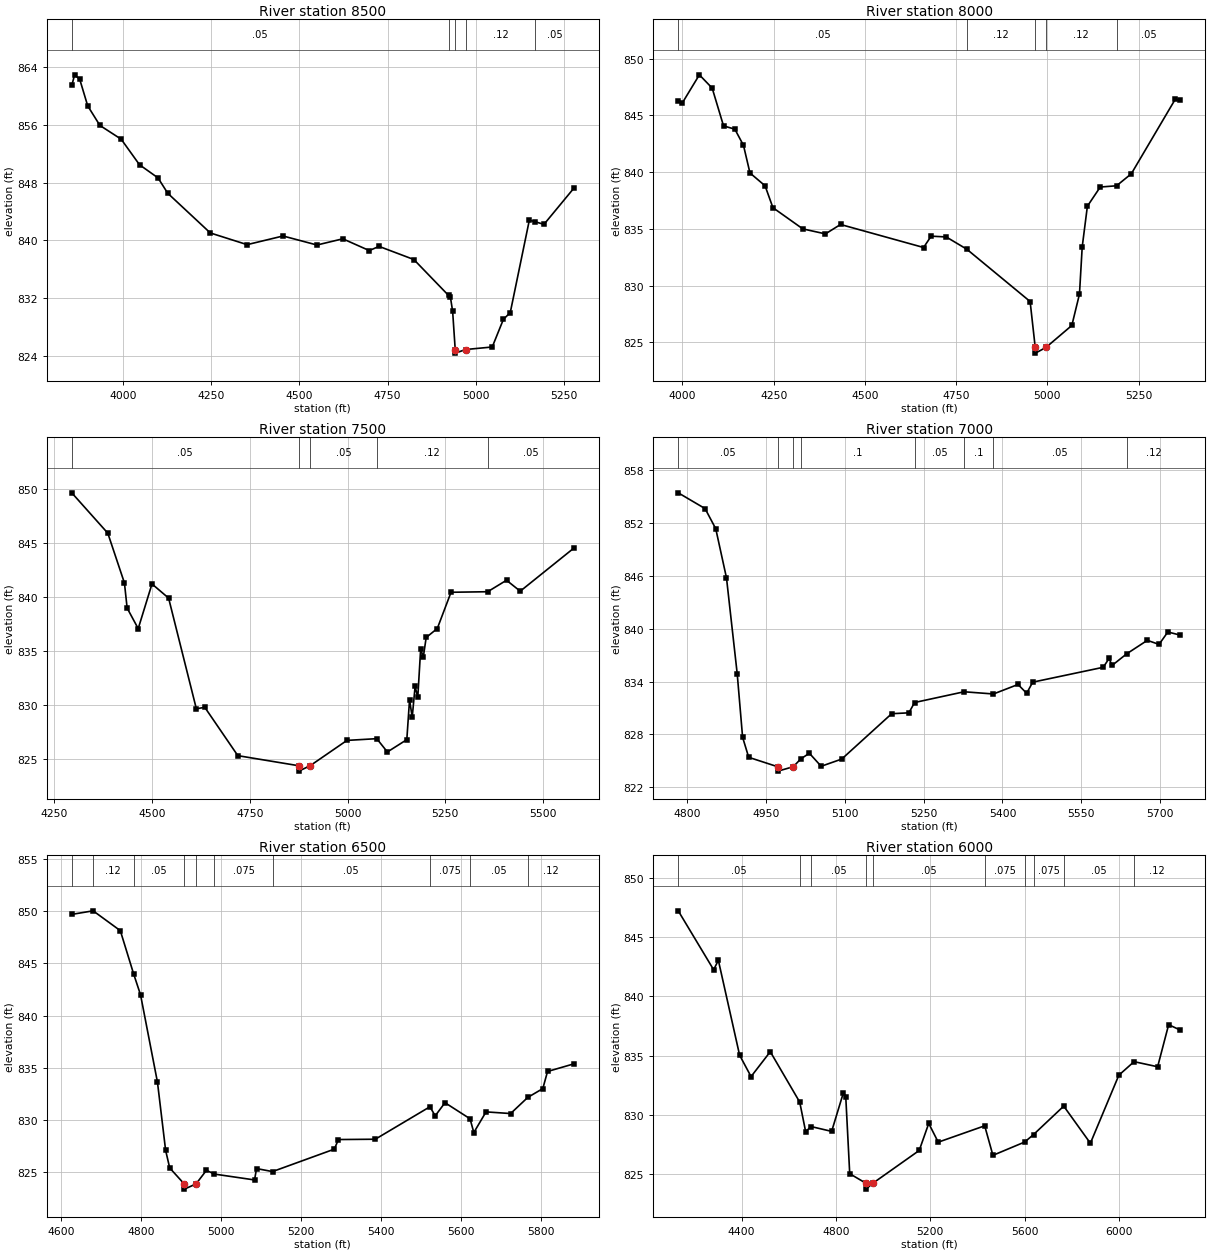
Type RM Length L Ch R = 1,8500,500,500,500
BEGIN DESCRIPTION:
PECAN CREEK 17.0
END DESCRIPTION:
XS GIS Cut Line= 3
      2909605.70     10168553.14      2910140.84     10169566.30
      2910405.68     10169653.11
#Sta/Elev= 30
  3854.2  861.46  3862.3  862.93  3876.8  862.31  3899.4  858.63  3934.0  855.92
  3994.4  854.01  4046.4  850.47  4098.9  848.65  4126.5  846.52  4247.3  841.02
  4351.7  839.40  4453.6  840.60  4549.9  839.35  4623.2  840.21  4698.3  838.58
  4726.0  839.16  4824.7  837.34  4923.3  832.36  4928.5  832.13  4934.8  830.17
  4942.1  824.87  4942.6  824.37  4971.5  824.87  5047.2  825.22  5078.8  829.05
  5098.3  829.99  5152.4  842.79  5169.2  842.57  5193.9  842.21  5278.7  847.22
#Mann=5,-1,0
  3854.2    0.05       0  4923.3    0.12       0  4942.1    0.07       0
  4971.5    0.12       0  5169.2    0.05       0
Bank Sta=4942.1,4971.5
Exp/Cntr=0.3,0.1

Type RM Length L Ch R = 1,8000,500,500,500
BEGIN DESCRIPTION:
PECAN CREEK 16.0
END DESCRIPTION:
XS GIS Cut Line= 3
      2909505.68     10168903.09      2909763.45     10169881.09
      2910005.66     10170153.08
#Sta/Elev= 30
  3988.6  846.28  3999.0  846.06  4046.5  848.58  4081.6  847.41  4112.7  844.08
  4143.7  843.79  4167.4  842.36  4185.1  839.93  4226.5  838.80  4248.0  836.87
  4329.9  835.00  4391.9  834.56  4433.3  835.39  4660.8  833.36  4681.5  834.36
  4722.9  834.29  4779.2  833.21  4952.7  828.60  4966.7  824.55  4967.2  824.05
  4996.1  824.55  5067.0  826.49  5087.9  829.25  5095.4  833.41  5109.6  837.00
  5144.8  838.69  5189.5  838.80  5230.0  839.86  5350.4  846.43  5364.2  846.33
#Mann=5,-1,0
  3988.6    0.05       0  4779.2    0.12       0  4966.7    0.07       0
  4996.1    0.12       0  5189.5    0.05       0
Bank Sta=4966.7,4996.1
Exp/Cntr=0.3,0.1

Type RM Length L Ch R = 1,7500,500,500,500
BEGIN DESCRIPTION:
PECAN CREEK 15.0
END DESCRIPTION:
XS GIS Cut Line= 3
      2908755.69     10169403.12      2909272.84     10169881.96
      2909665.94     10170306.25
#Sta/Elev= 30
  4295.2  849.64  4387.3  845.91  4429.8  841.31  4436.7  838.99  4465.0  837.09
  4500.2  841.22  4542.7  839.91  4613.6  829.68  4635.1  829.82  4719.6  825.35
  4875.0  824.42  4875.5  823.92  4904.4  824.42  4998.5  826.76  5074.7  826.92
  5101.8  825.69  5151.5  826.83  5158.5  830.52  5165.3  828.90  5172.7  831.75
  5179.5  830.73  5186.9  835.20  5193.7  834.47  5201.0  836.27  5229.4  837.10
  5264.5  840.45  5358.2  840.50  5406.3  841.56  5441.4  840.55  5578.4  844.53
#Mann=5,-1,0
  4295.2    0.05       0  4875.0    0.03       0  4904.4    0.05       0
  5074.7    0.12       0  5358.2    0.05       0
Bank Sta=4875,4904.4
Exp/Cntr=0.3,0.1

Type RM Length L Ch R = 1,7000,500,500,500
BEGIN DESCRIPTION:
PECAN CREEK 14.0
END DESCRIPTION:
XS GIS Cut Line= 3
      2908755.68     10169753.10      2908797.17     10169965.28
      2909456.66     10170296.30
#Sta/Elev= 30
  4783.8  855.43  4834.8  853.64  4855.1  851.35  4875.5  845.77  4895.9  834.87
  4906.1  827.68  4917.7  825.40  4972.7  824.33  4973.2  823.83  5002.4  824.33
  5016.7  825.22  5033.0  825.86  5055.4  824.38  5094.5  825.20  5189.4  830.35
  5222.1  830.45  5232.9  831.62  5327.0  832.84  5382.8  832.59  5429.5  833.67
  5445.9  832.67  5457.4  833.93  5591.4  835.62  5602.5  836.62  5608.2  835.83
  5636.0  837.15  5675.2  838.68  5697.5  838.22  5714.2  839.63  5737.9  839.27
#Mann=8,-1,0
  4783.8    0.05       0  4972.7    0.03       0  5002.4    0.05       0
  5016.7     0.1       0  5232.9    0.05       0  5327.0     0.1       0
  5382.8    0.05       0  5636.0    0.12       0
Bank Sta=4972.7,5002.4
Exp/Cntr=0.3,0.1

Type RM Length L Ch R = 1,6500,500,500,500
BEGIN DESCRIPTION:
PECAN CREEK 13.0
END DESCRIPTION:
XS GIS Cut Line= 3
      2908305.69     10169853.13      2908380.25     10170219.72
      2909239.87     10170414.44
#Sta/Elev= 30
  4625.9  849.69  4679.3  850.03  4747.3  848.13  4780.4  844.01  4797.9  841.98
  4840.2  833.61  4860.6  827.08  4870.8  825.40  4907.0  823.87  4907.5  823.37
  4936.7  823.87  4962.6  825.17  4982.8  824.81  5082.9  824.25  5088.0  825.34
  5127.9  825.05  5282.4  827.20  5292.7  828.12  5384.9  828.15  5521.5  831.26
  5534.7  830.39  5559.2  831.65  5621.8  830.11  5631.3  828.79  5661.8  830.77
  5723.3  830.61  5766.3  832.16  5803.8  833.00  5815.6  834.64  5881.4  835.37
#Mann=10,-1,0
  4625.9    0.05       0  4679.3    0.12       0  4780.4    0.05       0
  4907.0    0.07       0  4936.7    0.05       0  4982.8   0.075       0
  5127.9    0.05       0  5521.5   0.075       0  5621.8    0.05       0
  5766.3    0.12       0
Bank Sta=4907,4936.7
Exp/Cntr=0.3,0.1

Type RM Length L Ch R = 1,6000,500,500,500
BEGIN DESCRIPTION:
PECAN CREEK 12.0
END DESCRIPTION:
XS GIS Cut Line= 4
      2907255.67     10170603.11      2908123.77     10170561.40
      2909032.37     10170441.76      2909374.86     10170478.55
#Sta/Elev= 30
  4130.9  847.21  4281.1  842.24  4301.1  843.04  4391.2  835.04  4439.8  833.23
  4521.4  835.33  4646.3  831.08  4671.5  828.58  4693.7  829.02  4781.7  828.61
  4831.7  831.88  4841.7  831.49  4858.4  825.04  4926.9  824.24  4927.4  823.74
  4956.8  824.24  5153.2  827.00  5193.6  829.28  5233.9  827.70  5431.0  829.08
  5465.9  826.59  5600.4  827.71  5638.1  828.34  5766.3  830.74  5879.4  827.61
  6000.2  833.35  6064.7  834.49  6164.7  834.06  6211.4  837.61  6260.9  837.15
#Mann=10,-1,0
  4130.9    0.05       0  4646.3    0.12       0  4693.7    0.05       0
  4926.9    0.03       0  4956.8    0.05       0  5431.0   0.075       0
  5600.4    0.05       0  5638.1   0.075       0  5766.3    0.05       0
  6064.7    0.12       0
Bank Sta=4926.9,4956.8
Exp/Cntr=0.3,0.1

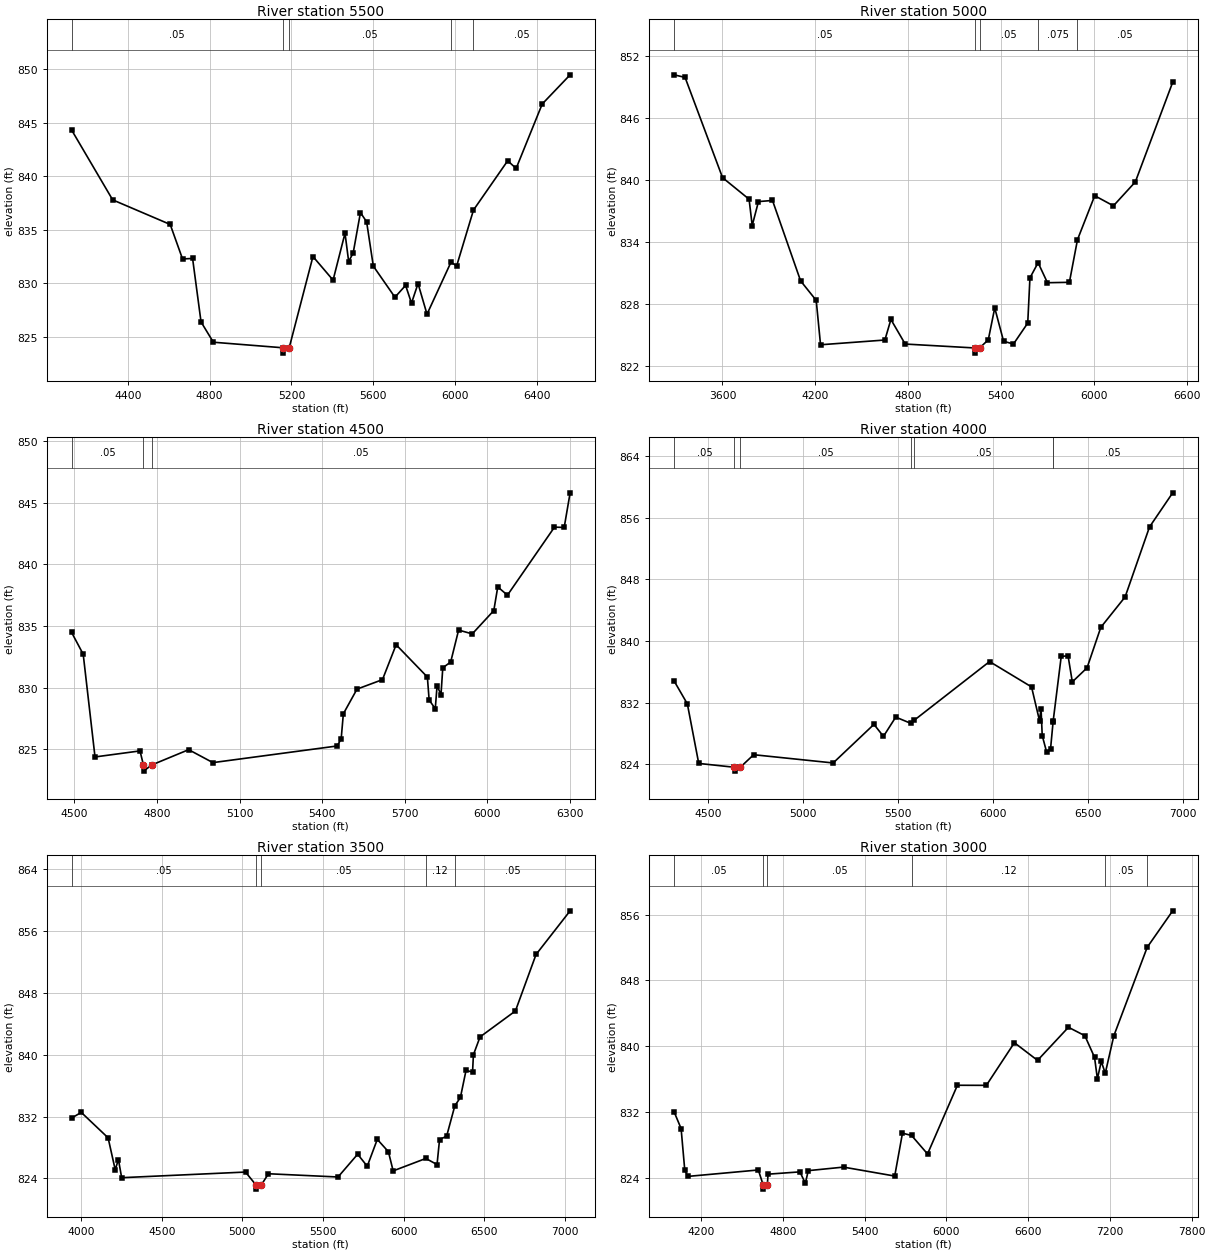
Type RM Length L Ch R = 1,5500,500,500,500
BEGIN DESCRIPTION:
PECAN CREEK 11.0
END DESCRIPTION:
XS GIS Cut Line= 3
      2907505.72     10170903.12      2908376.48     10170983.91
      2909805.67     10170353.12
#Sta/Elev= 30
  4125.5  844.34  4326.3  837.80  4607.5  835.50  4667.8  832.27  4716.9  832.32
  4758.2  826.38  4818.4  824.48  5158.9  823.96  5159.4  823.46  5189.1  823.96
  5305.2  832.50  5403.6  830.29  5461.9  834.68  5479.8  832.03  5501.9  832.84
  5537.3  836.61  5567.5  835.75  5600.3  831.60  5706.0  828.69  5758.1  829.80
  5786.9  828.14  5818.9  829.97  5862.7  827.10  5979.9  831.97  6007.6  831.62
  6089.9  836.85  6257.1  841.46  6298.3  840.74  6425.8  846.77  6562.2  849.50
#Mann=5,-1,0
  4125.5    0.05       0  5158.9    0.03       0  5189.1    0.05       0
  5979.9    0.12       0  6089.9    0.05       0
Bank Sta=5158.9,5189.1
Exp/Cntr=0.3,0.1

Type RM Length L Ch R = 1,5000,500,500,500
BEGIN DESCRIPTION:
PECAN CREEK 10.0
END DESCRIPTION:
XS GIS Cut Line= 3
      2906955.73     10171603.11      2908653.10     10171377.54
      2909805.69     10170403.11
#Sta/Elev= 30
  3287.7  850.17  3358.3  849.92  3600.4  840.21  3771.9  838.12  3792.1  835.57
  3832.4  837.89  3923.2  838.00  4104.8  830.21  4205.7  828.32  4233.7  824.02
  4649.5  824.48  4688.4  826.47  4780.7  824.09  5231.1  823.71  5231.6  823.21
  5261.4  823.71  5317.7  824.50  5359.4  827.59  5416.6  824.36  5480.3  824.09
  5572.6  826.12  5586.9  830.50  5639.6  831.97  5700.0  830.03  5841.8  830.07
  5894.1  834.20  6005.5  838.46  6126.4  837.48  6268.1  839.80  6509.3  849.45
#Mann=5,-1,0
  3287.7    0.05       0  5231.1    0.03       0  5261.4    0.05       0
  5639.6   0.075       0  5894.1    0.05       0
Bank Sta=5231.1,5261.4
Exp/Cntr=0.3,0.1

Type RM Length L Ch R = 1,4500,500,500,500
BEGIN DESCRIPTION:
PECAN CREEK 9.0
END DESCRIPTION:
XS GIS Cut Line= 3
      2908755.70     10172003.09      2909086.74     10171614.47
      2909905.71     10170603.07
#Sta/Elev= 30
  4489.5  834.49  4531.7  832.72  4574.6  824.39  4738.2  824.88  4750.5  823.74
  4751.0  823.24  4780.8  823.74  4915.0  824.98  5003.1  823.93  5454.9  825.28
  5469.3  825.86  5477.2  827.89  5526.8  829.89  5619.4  830.66  5669.0  833.49
  5782.6  830.87  5789.0  829.01  5811.3  828.30  5817.8  830.16  5832.1  829.45
  5838.6  831.62  5867.3  832.09  5896.1  834.68  5945.7  834.37  6024.0  836.26
  6038.4  838.18  6073.6  837.51  6244.6  843.03  6279.8  843.00  6301.4  845.81
#Mann=3,-1,0
  4489.5    0.05       0  4750.5    0.03       0  4780.8    0.05       0
Bank Sta=4750.5,4780.8
Exp/Cntr=0.3,0.1

Type RM Length L Ch R = 1,4000,500,500,500
BEGIN DESCRIPTION:
PECAN CREEK 8.0
END DESCRIPTION:
XS GIS Cut Line= 3
      2908855.67     10172153.12      2909486.87     10171908.33
      2910655.71     10170353.08
#Sta/Elev= 30
  4323.0  834.80  4392.4  831.84  4452.3  824.11  4640.3  823.61  4640.8  823.11
  4670.7  823.61  4741.3  825.24  5159.5  824.17  5374.0  829.18  5424.0  827.62
  5488.6  830.12  5568.2  829.31  5586.7  829.73  5982.2  837.33  6203.0  834.04
  6244.9  829.66  6253.0  831.23  6259.2  827.73  6282.1  825.61  6302.9  825.97
  6316.5  829.53  6316.7  829.59  6359.2  838.00  6395.1  838.08  6417.5  834.69
  6495.1  836.52  6567.4  841.77  6695.3  845.72  6823.6  854.80  6945.5  859.23
#Mann=7,-1,0
  4323.0    0.05       0  4640.3    0.03       0  4670.7    0.05       0
  5568.2   0.075       0  5586.7    0.05       0  6316.5    0.12       0
  6316.7    0.05       0
Bank Sta=4640.3,4670.7
Exp/Cntr=0.3,0.1

Type RM Length L Ch R = 1,3500,500,500,500
BEGIN DESCRIPTION:
PECAN CREEK 7.0
END DESCRIPTION:
XS GIS Cut Line= 4
      2908825.69     10172312.71      2909165.42     10172290.86
      2909879.85     10172211.10      2910705.70     10170353.07
#Sta/Elev= 30
  3940.7  831.82  4000.8  832.55  4167.2  829.26  4211.3  825.13  4231.3  826.45
  4251.3  824.10  5019.7  824.83  5085.9  823.12  5086.4  822.62  5116.3  823.12
  5161.9  824.61  5593.6  824.19  5715.3  827.14  5774.8  825.58  5837.1  829.06
  5906.1  827.46  5935.5  824.98  6138.2  826.59  6207.7  825.80  6223.4  829.04
  6267.2  829.47  6318.1  833.41  6352.7  834.48  6387.6  837.99  6428.0  837.77
  6433.4  840.01  6474.5  842.32  6694.0  845.68  6821.9  852.99  7033.3  858.64
#Mann=5,-1,0
  3940.7    0.05       0  5085.9    0.03       0  5116.3    0.05       0
  6138.2    0.12       0  6318.1    0.05       0
Bank Sta=5085.9,5116.3
Exp/Cntr=0.3,0.1

Type RM Length L Ch R = 1,3000,0,0,0
BEGIN DESCRIPTION:
PECAN CREEK 6.0
END DESCRIPTION:
XS GIS Cut Line= 4
      2909160.78     10172628.32      2909401.57     10172786.13
      2910099.73     10172652.12      2911855.67     10170653.13
#Sta/Elev= 30
  4001.2  831.98  4052.2  829.96  4079.3  824.86  4102.7  824.14  4619.1  824.92
  4654.8  823.09  4655.3  822.59  4685.3  823.09  4690.4  824.41  4924.6  824.69
  4964.2  823.30  4985.7  824.84  5244.4  825.27  5620.2  824.18  5677.1  829.40
  5744.0  829.12  5861.2  826.87  6080.4  835.23  6292.9  835.22  6498.8  840.41
  6668.7  838.26  6895.5  842.29  7016.0  841.26  7087.1  838.63  7108.0  836.02
  7136.5  838.13  7165.8  836.69  7228.5  841.24  7473.6  852.02  7660.7  856.46
#Mann=6,-1,0
  4001.2    0.05       0  4654.8    0.03       0  4685.3    0.05       0
  5744.0    0.12       0  7165.8    0.05       0  7473.6    0.12       0
Bank Sta=4654.8,4685.3
Exp/Cntr=0.3,0.1

Chan Stop Cuts=-1