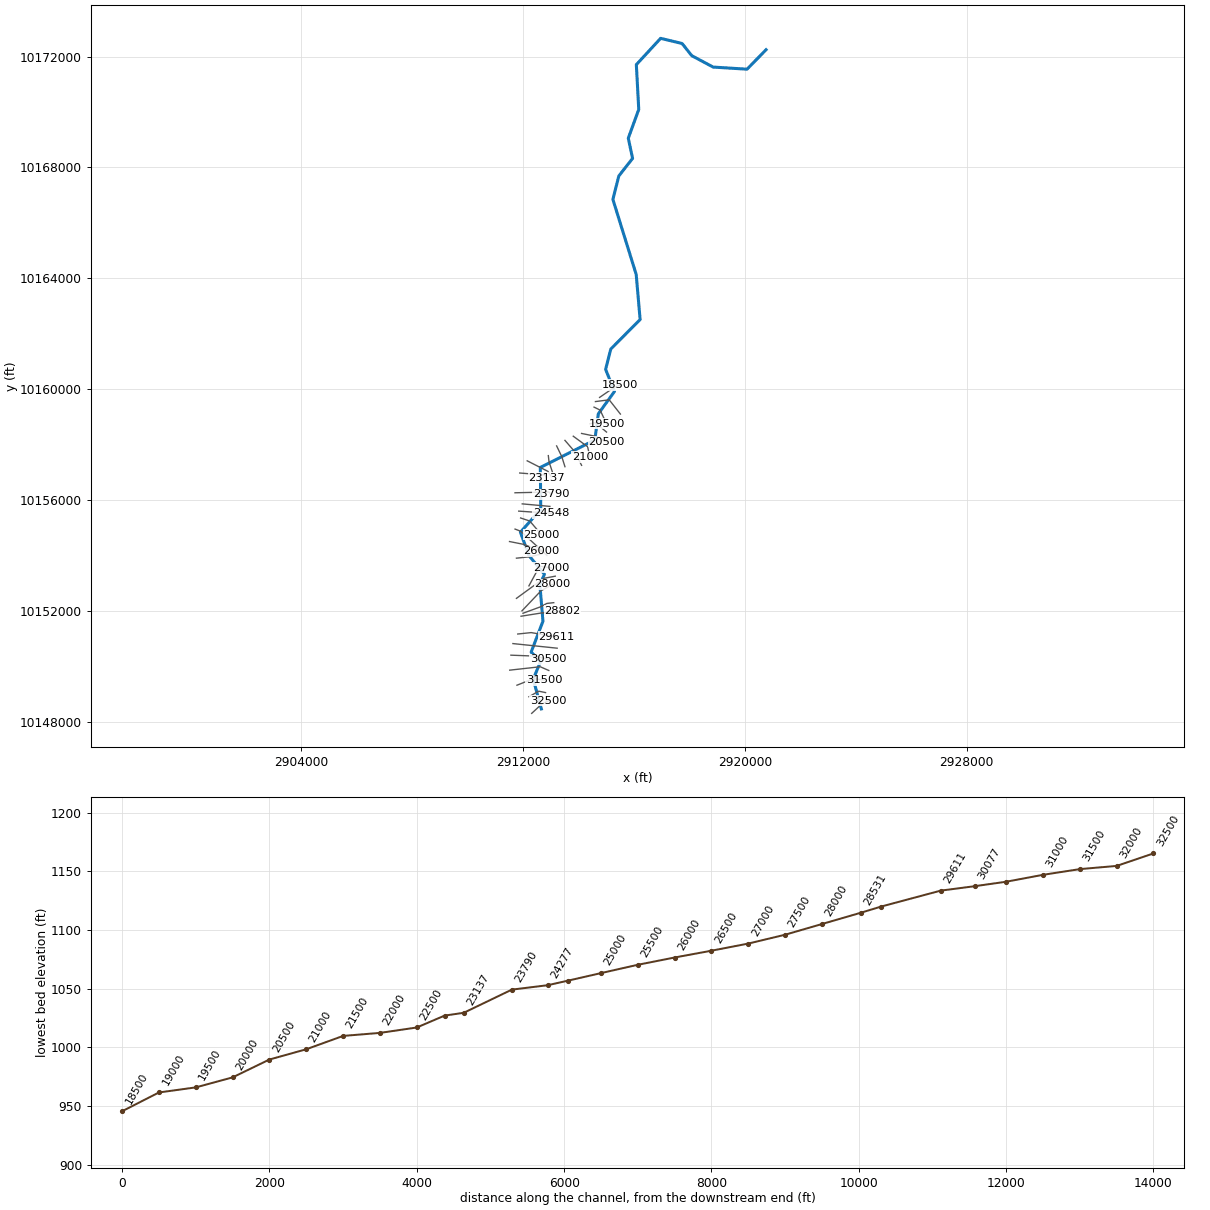
--- SLICKROCK CREEK.prj (project) ---

Proj Title=SLICKROCK CREEK Base Level Engineering
Current Plan=p01
Default Exp/Contr=0.3,0.1
English Units
Geom File=g01
Flow File=f01
Plan File=p01
Y Axis Title=Elevation
X Axis Title(PF)=Main Channel Distance
X Axis Title(XS)=Station
BEGIN DESCRIPTION:
SLICKROCK CREEK
END DESCRIPTION:
DSS Export Rating Curves= 0
DSS Export Rating Curve Sorted= 0
DSS Export Volume Flow Curves= 0
DXF OffsetX= 0
DXF OffsetY= 0
DXF ScaleX= 1
DXF ScaleY= 10

--- SLICKROCK CREEK.p01 (plan) ---

Plan Title=Multiple Run
Short Identifier=Multiple
Geom File=g01
Flow File=f01
Subcritical Flow
K Sum by GR= 0
Std Step Tol= 0.01
Critical Tol= 0.01
Num of Std Step Trials= 20
Max Error Tol= 0.3
Flow Tol Ratio= 0.001
Split Flow NTrial= 30
Split Flow Tol= 0.02
Split Flow Ratio= 0.02
Log Output Level= 0
Friction Slope Method= 1
Unsteady Friction Slope Method= 2
Unsteady Bridges Friction Slope Method= 1
Parabolic Critical Depth
Global Vel Dist=  1 , 1 , 1
Global Log Level= 0
CheckData=True
Encroach Param= -1, 0, 0, 0
BEGIN DESCRIPTION:
Multiple Run
END DESCRIPTION:

--- SLICKROCK CREEK.f01 (steady flow) ---

Flow Title=Multiple
Program Version=4.10
Number of Profiles= 7
Profile Names=10-year,25-year,50-year,1pct_min,100-year,1pct_plu,500-year
River Rch & RM=SLICKROCK CREEK,Reach-1         ,32500
    1080    1868    3340    2355    4756    9608    6771
River Rch & RM=SLICKROCK CREEK,Reach-1         ,30077
    1352    2365    4507    3199    6494   13182    9254
River Rch & RM=SLICKROCK CREEK,Reach-1         ,27500
    1835    3265    6806    4864    9977   20462   14259
River Rch & RM=SLICKROCK CREEK,Reach-1         ,22500
    2070    3719    8003    5671   11829   24673   16981
River Rch & RM=SLICKROCK CREEK,Reach-1         ,18000
    2350    4266    9351    6526   13928   29728   20080
River Rch & RM=SLICKROCK CREEK,Reach-1         ,12000
    2641    4839   10286    7047   15332   33358   22033
Boundary for River Rch & Prof#=SLICKROCK CREEK,Reach-1         , 1
Up Type= 0
Dn Type= 3
Dn Slope=0.0005
Boundary for River Rch & Prof#=SLICKROCK CREEK,Reach-1         , 2
Up Type= 0
Dn Type= 3
Dn Slope=0.0005
Boundary for River Rch & Prof#=SLICKROCK CREEK,Reach-1         , 3
Up Type= 0
Dn Type= 3
Dn Slope=0.0005
Boundary for River Rch & Prof#=SLICKROCK CREEK,Reach-1         , 4
Up Type= 0
Dn Type= 3
Dn Slope=0.0005
Boundary for River Rch & Prof#=SLICKROCK CREEK,Reach-1         , 5
Up Type= 0
Dn Type= 3
Dn Slope=0.0005
Boundary for River Rch & Prof#=SLICKROCK CREEK,Reach-1         , 6
Up Type= 0
Dn Type= 3
Dn Slope=0.0005
Boundary for River Rch & Prof#=SLICKROCK CREEK,Reach-1         , 7
Up Type= 0
Dn Type= 3
Dn Slope=0.0005
DSS Import GetInterval= 0
DSS Import GetPeak= 0
DSS Import FillOption= 0

--- SLICKROCK CREEK.g01 (geometry) ---

Geom Title=Existing Conditions

River Reach=SLICKROCK CREEK,Reach-1
Reach XY= 30
      2912653.75     10148464.00      2912362.25     10149536.00
      2912623.75     10150175.00      2912285.75     10150513.00
      2912712.75     10151629.00      2912601.00     10152939.00
      2912765.50     10153322.00      2912211.50     10153991.00
      2911899.00     10154839.00      2912633.25     10155668.00
      2912617.75     10157175.00      2914583.75     10158167.00
      2914710.50     10159112.00      2915292.75     10159918.00
      2914972.25     10160715.00      2915160.25     10161449.00
      2916218.00     10162513.00      2916076.50     10164139.00
      2915235.50     10166847.00      2915450.00     10167694.00
      2915945.75     10168327.00      2915791.25     10169055.00
      2916168.75     10170094.00      2916081.50     10171710.00
      2916957.75     10172659.00      2917731.25     10172473.00
      2918082.00     10172033.00      2918852.75     10171622.00
      2920076.75     10171546.00      2920762.75     10172249.00

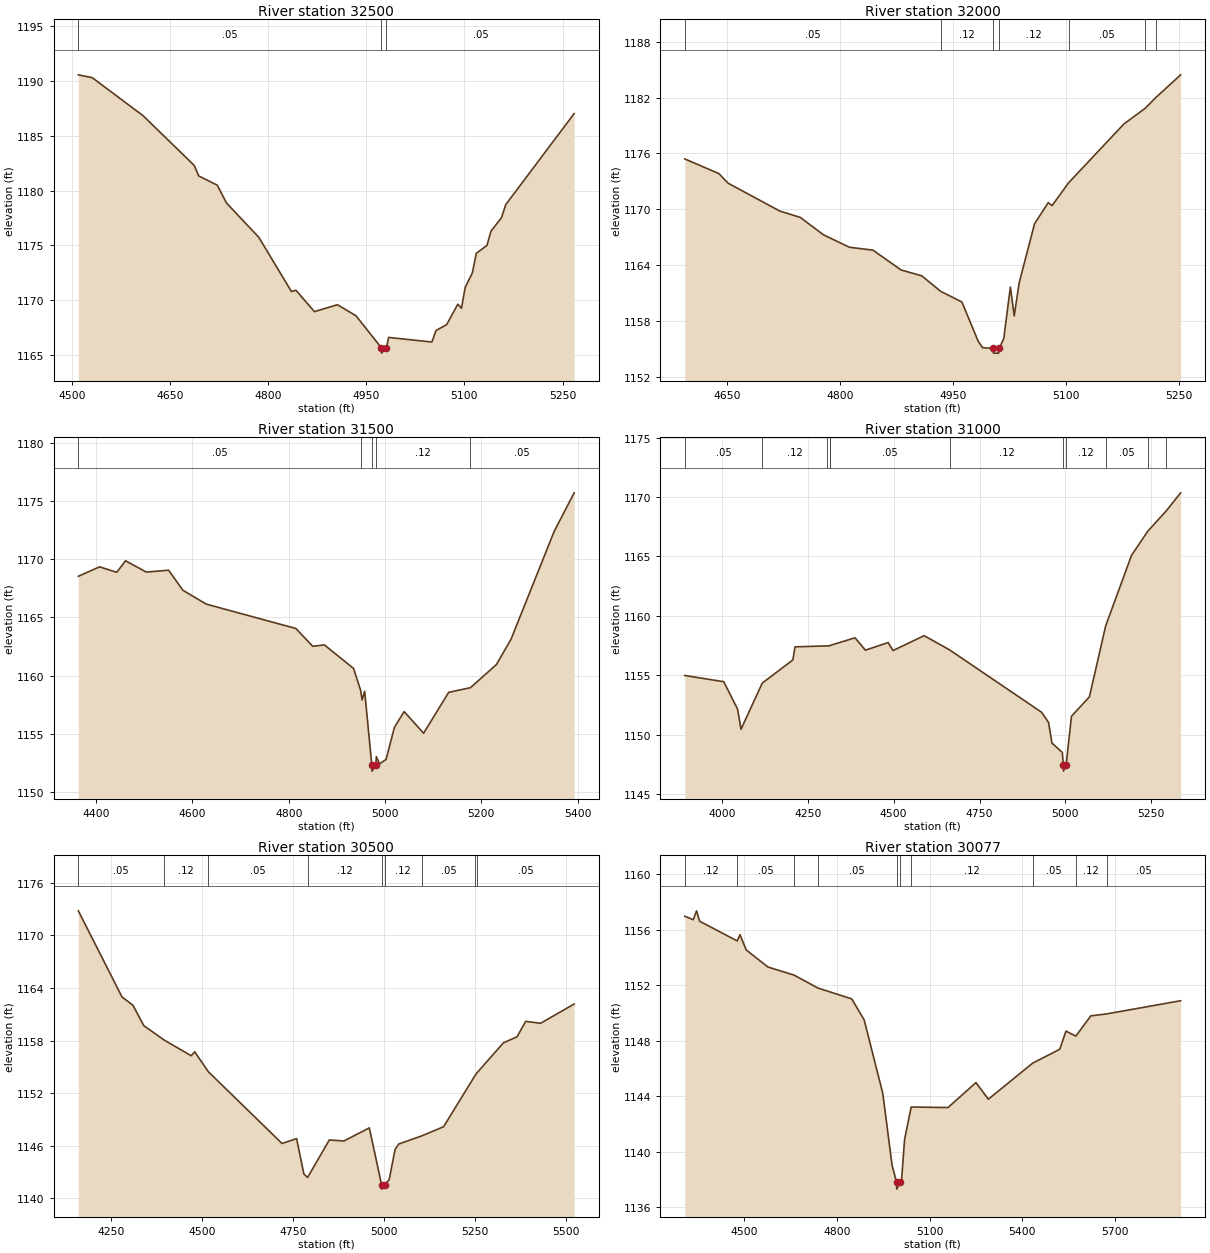
Type RM Length L Ch R = 1,32500,500,500,500
BEGIN DESCRIPTION:
SLICKROCK CREEK 65.0
END DESCRIPTION:
XS GIS Cut Line= 3
      2912305.68     10148303.11      2912664.71     10148636.56
      2912905.71     10148753.12
#Sta/Elev= 30
  4510.0 1190.54  4531.3 1190.28  4608.9 1186.82  4687.1 1182.29  4694.0 1181.33
  4722.3 1180.49  4736.5 1178.86  4785.8 1175.74  4835.7 1170.80  4842.5 1170.92
  4870.8 1168.97  4906.0 1169.60  4934.4 1168.59  4972.9 1165.69  4973.4 1165.19
  4980.9 1165.69  4984.2 1166.62  5050.3 1166.20  5056.6 1167.25  5072.9 1167.79
  5089.9 1169.65  5095.5 1169.28  5101.1 1171.16  5112.2 1172.51  5118.1 1174.28
  5134.4 1175.00  5140.6 1176.30  5156.6 1177.52  5163.2 1178.72  5267.7 1187.01
#Mann=3,-1,0
  4510.0    0.05       0  4972.9    0.05       0  4980.9    0.05       0
Bank Sta=4972.9,4980.9
Exp/Cntr=0.3,0.1

Type RM Length L Ch R = 1,32000,500,500,500
BEGIN DESCRIPTION:
SLICKROCK CREEK 64.0
END DESCRIPTION:
XS GIS Cut Line= 3
      2912205.71     10148903.13      2912558.30     10149104.22
      2912805.68     10149053.11
#Sta/Elev= 30
  4594.1 1175.41  4639.4 1173.83  4651.6 1172.80  4720.1 1169.81  4747.5 1169.12
  4778.3 1167.25  4812.8 1165.91  4844.0 1165.60  4881.4 1163.47  4908.8 1162.84
  4934.0 1161.17  4962.1 1160.03  4983.7 1155.82  4989.5 1155.12  5003.5 1155.03
  5004.0 1154.53  5011.0 1154.53  5011.5 1155.03  5017.7 1156.09  5026.5 1161.63
  5031.6 1158.54  5038.2 1162.09  5058.6 1168.44  5076.8 1170.71  5081.9 1170.39
  5103.8 1172.84  5177.2 1179.16  5205.5 1180.85  5220.2 1182.05  5252.6 1184.45
#Mann=7,-1,0
  4594.1    0.05       0  4934.0    0.12       0  5003.5    0.07       0
  5011.5    0.12       0  5103.8    0.05       0  5205.5    0.12       0
  5220.2    0.05       0
Bank Sta=5003.5,5011.5
Exp/Cntr=0.3,0.1

Type RM Length L Ch R = 1,31500,500,500,500
BEGIN DESCRIPTION:
SLICKROCK CREEK 63.0
END DESCRIPTION:
XS GIS Cut Line= 3
      2911774.53     10149319.48      2912366.31     10149555.20
      2912755.64     10149503.12
#Sta/Elev= 30
  4363.0 1168.53  4407.3 1169.34  4442.7 1168.87  4461.1 1169.86  4504.2 1168.89
  4550.5 1169.05  4580.2 1167.33  4628.7 1166.14  4814.8 1164.05  4849.9 1162.52
  4874.1 1162.64  4934.7 1160.62  4949.3 1158.74  4952.4 1157.92  4957.7 1158.66
  4972.6 1152.31  4973.1 1151.81  4980.7 1152.31  4982.0 1153.05  4988.6 1152.43
  5002.2 1152.82  5019.5 1155.57  5039.7 1156.92  5080.1 1155.06  5132.2 1158.57
  5177.4 1158.97  5231.4 1160.96  5261.7 1163.13  5351.3 1172.38  5392.8 1175.69
#Mann=5,-1,0
  4363.0    0.05       0  4949.3    0.12       0  4972.6    0.07       0
  4980.7    0.12       0  5177.4    0.05       0
Bank Sta=4972.6,4980.7
Exp/Cntr=0.3,0.1

Type RM Length L Ch R = 1,31000,500,500,500
BEGIN DESCRIPTION:
SLICKROCK CREEK 62.0
END DESCRIPTION:
XS GIS Cut Line= 3
      2911512.96     10149862.38      2912614.43     10149985.22
      2912922.21     10149851.16
#Sta/Elev= 30
  3891.7 1154.99  4005.1 1154.47  4045.4 1152.17  4055.4 1150.47  4117.3 1154.35
  4206.4 1156.30  4212.7 1157.40  4305.5 1157.48  4314.8 1157.49  4316.0 1157.53
  4387.5 1158.16  4417.7 1157.12  4483.9 1157.76  4498.2 1157.09  4588.7 1158.34
  4662.6 1157.15  4930.8 1151.90  4951.0 1151.05  4961.0 1149.31  4991.2 1148.52
  4994.1 1147.45  4994.6 1146.95  5002.2 1147.45  5017.8 1151.56  5070.1 1153.20
  5117.5 1159.17  5192.7 1165.09  5240.0 1167.12  5294.4 1168.85  5335.7 1170.35
#Mann=11,-1,0
  3891.7    0.05       0  4117.3    0.12       0  4305.5    0.05       0
  4314.8    0.12       0  4316.0    0.05       0  4662.6    0.12       0
  4994.1    0.07       0  5002.2    0.12       0  5117.5    0.05       0
  5240.0    0.12       0  5294.4    0.05       0
Bank Sta=4994.1,5002.2
Exp/Cntr=0.3,0.1

Type RM Length L Ch R = 1,30500,423,423,423
BEGIN DESCRIPTION:
SLICKROCK CREEK 61.0
END DESCRIPTION:
XS GIS Cut Line= 3
      2911555.66     10150403.11      2912396.25     10150371.06
      2912905.67     10150253.11
#Sta/Elev= 30
  4158.8 1172.81  4278.9 1162.99  4308.9 1162.04  4339.0 1159.71  4394.9 1158.07
  4469.1 1156.28  4479.1 1156.72  4516.6 1154.45  4719.2 1146.27  4759.3 1146.82
  4779.3 1142.79  4789.5 1142.39  4849.3 1146.67  4889.4 1146.55  4959.4 1148.05
  4993.1 1141.56  4993.6 1141.06  5001.3 1141.56  5013.9 1142.12  5030.2 1145.59
  5040.5 1146.21  5103.3 1147.13  5163.7 1148.18  5250.1 1154.01  5254.6 1154.28
  5328.2 1157.75  5365.8 1158.44  5389.5 1160.20  5430.5 1159.98  5522.9 1162.18
#Mann=9,-1,0
  4158.8    0.05       0  4394.9    0.12       0  4516.6    0.05       0
  4789.5    0.12       0  4993.1    0.07       0  5001.3    0.12       0
  5103.3    0.05       0  5250.1    0.12       0  5254.6    0.05       0
Bank Sta=4993.1,5001.3
Exp/Cntr=0.3,0.1

Type RM Length L Ch R = 1,30077,466,466,466
BEGIN DESCRIPTION:
Mapping XS a281a4b7
END DESCRIPTION:
XS GIS Cut Line= 2
      2911627.89     10150821.40      2913224.94     10150654.96
#Sta/Elev= 30
  4307.1 1156.96  4334.4 1156.71  4345.1 1157.35  4355.2 1156.60  4476.9 1155.18
  4485.9 1155.63  4506.0 1154.53  4576.3 1153.30  4660.8 1152.72  4737.8 1151.79
  4847.8 1151.00  4888.0 1149.49  4948.3 1144.19  4978.5 1138.99  4993.0 1137.79
  4993.5 1137.29  5004.3 1137.79  5008.7 1137.84  5018.9 1140.87  5040.2 1143.21
  5159.5 1143.17  5250.0 1144.97  5290.2 1143.77  5433.5 1146.37  5521.4 1147.37
  5541.5 1148.68  5573.5 1148.32  5622.0 1149.78  5673.2 1149.92  5912.8 1150.87
#Mann=10,-1,0
  4307.1    0.12       0  4476.9    0.05       0  4660.8    0.12       0
  4737.8    0.05       0  4993.0    0.05       0  5004.3    0.05       0
  5040.2    0.12       0  5433.5    0.05       0  5573.5    0.12       0
  5673.2    0.05       0
Bank Sta=4993,5004.3
Exp/Cntr=0.3,0.1

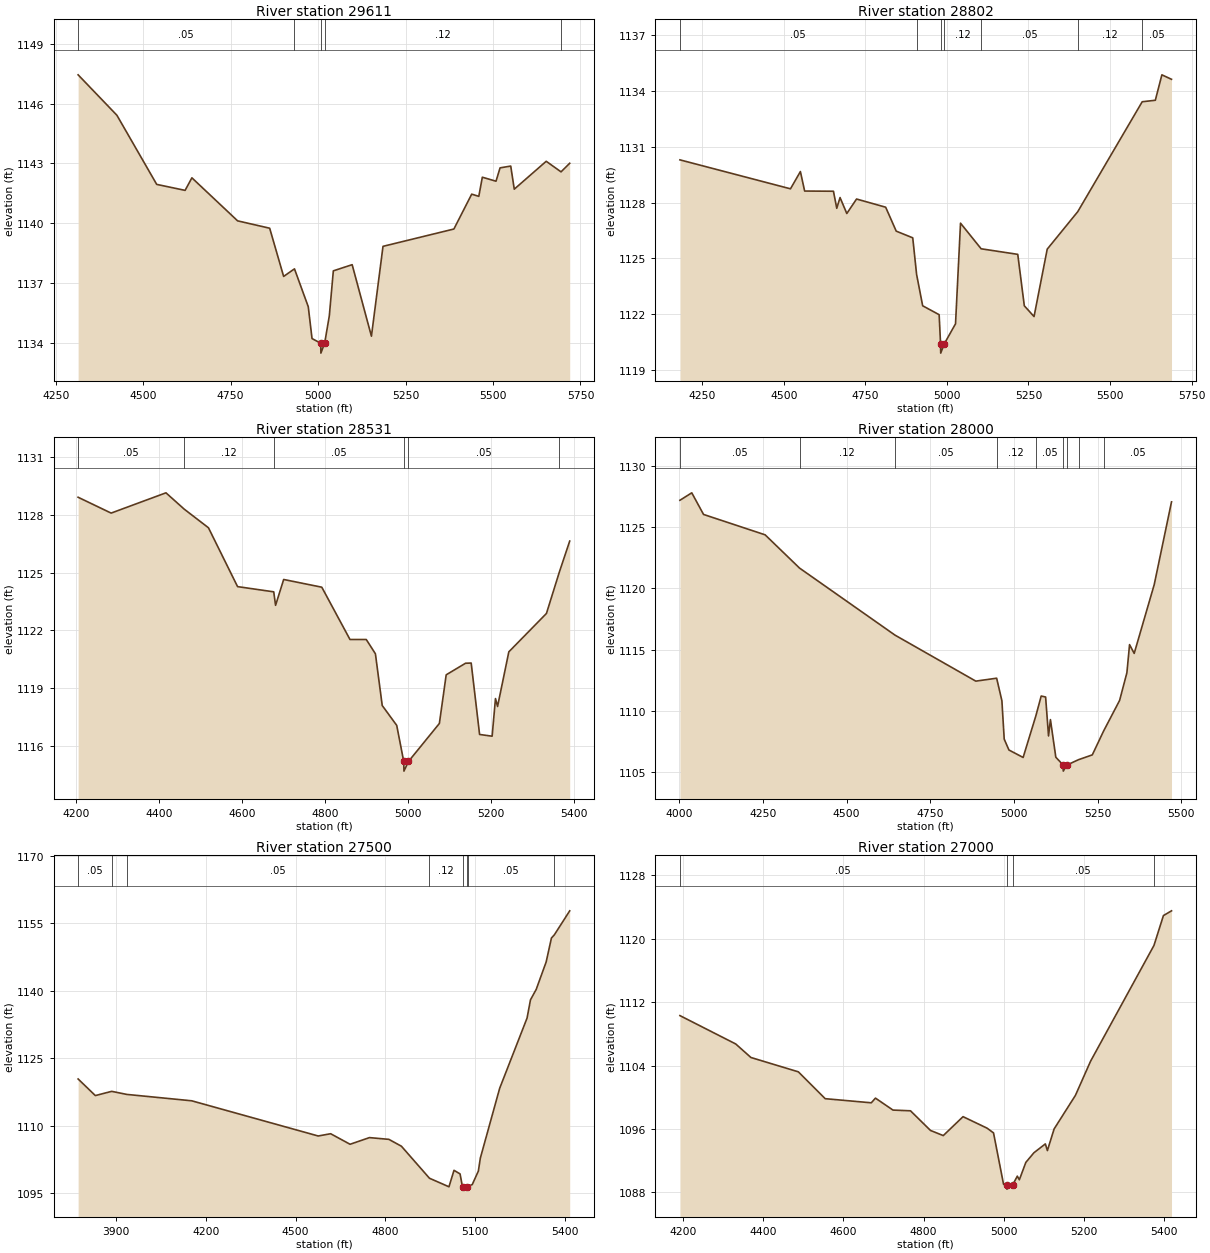
Type RM Length L Ch R = 1,29611,809,809,809
BEGIN DESCRIPTION:
Mapping XS df9ee444
END DESCRIPTION:
XS GIS Cut Line= 3
      2911802.22     10151166.16      2912285.72     10151217.68
      2913191.93     10151063.35
#Sta/Elev= 30
  4313.8 1147.44  4424.7 1145.41  4538.5 1141.94  4619.7 1141.64  4639.1 1142.27
  4769.8 1140.11  4861.5 1139.74  4901.4 1137.32  4932.4 1137.70  4971.8 1135.80
  4982.6 1134.20  5007.4 1133.97  5007.9 1133.47  5018.7 1133.97  5032.0 1135.34
  5043.5 1137.60  5097.3 1137.91  5152.4 1134.32  5185.5 1138.83  5388.2 1139.70
  5439.1 1141.45  5459.4 1141.34  5469.5 1142.30  5508.6 1142.10  5520.2 1142.77
  5550.7 1142.86  5560.8 1141.70  5652.1 1143.10  5694.5 1142.57  5719.3 1143.00
#Mann=5,-1,0
  4313.8    0.05       0  4932.4    0.12       0  5007.4    0.07       0
  5018.7    0.12       0  5694.5    0.05       0
Bank Sta=5007.4,5018.7
Exp/Cntr=0.3,0.1

Type RM Length L Ch R = 1,28802,271,271,271
BEGIN DESCRIPTION:
Mapping XS a999eab0
END DESCRIPTION:
XS GIS Cut Line= 3
      2911921.12     10151808.15      2912689.93     10151931.00
      2913415.10     10151994.40
#Sta/Elev= 30
  4181.8 1130.30  4520.6 1128.74  4551.0 1129.67  4564.0 1128.62  4652.3 1128.61
  4662.4 1127.69  4672.5 1128.27  4693.2 1127.41  4723.1 1128.19  4812.3 1127.75
  4844.7 1126.46  4895.3 1126.10  4907.1 1124.13  4925.7 1122.44  4976.2 1121.96
  4980.5 1120.39  4981.0 1119.89  4991.9 1120.39  5026.4 1121.47  5041.7 1126.89
  5104.9 1125.51  5217.1 1125.21  5237.2 1122.44  5267.0 1121.86  5307.4 1125.49
  5401.0 1127.51  5598.5 1133.43  5638.7 1133.51  5658.8 1134.88  5688.3 1134.64
#Mann=7,-1,0
  4181.8    0.05       0  4907.1    0.12       0  4980.5    0.07       0
  4991.9    0.12       0  5104.9    0.05       0  5401.0    0.12       0
  5598.5    0.05       0
Bank Sta=4980.5,4991.9
Exp/Cntr=0.3,0.1

Type RM Length L Ch R = 1,28531,531,531,531
BEGIN DESCRIPTION:
Mapping XS 0c9480cb
END DESCRIPTION:
XS GIS Cut Line= 4
      2911991.06     10151915.67      2912616.01     10152144.82
      2912852.12     10152269.82      2913101.39     10152297.51
#Sta/Elev= 30
  4205.1 1128.90  4284.6 1128.08  4416.6 1129.13  4460.8 1128.28  4518.9 1127.32
  4589.0 1124.27  4676.1 1124.00  4680.5 1123.30  4700.0 1124.64  4791.8 1124.24
  4859.7 1121.53  4898.9 1121.53  4920.9 1120.79  4937.3 1118.11  4972.2 1117.08
  4989.1 1115.21  4989.6 1114.71  5000.5 1115.21  5074.9 1117.18  5091.3 1119.70
  5137.9 1120.30  5151.5 1120.31  5171.7 1116.61  5201.9 1116.52  5210.0 1118.47
  5215.0 1118.06  5242.1 1120.89  5332.7 1122.88  5364.0 1125.04  5388.7 1126.63
#Mann=6,-1,0
  4205.1    0.05       0  4460.8    0.12       0  4676.1    0.05       0
  4989.1    0.05       0  5000.5    0.05       0  5364.0    0.12       0
Bank Sta=4989.1,5000.5
Exp/Cntr=0.3,0.1

Type RM Length L Ch R = 1,28000,500,500,500
BEGIN DESCRIPTION:
SLICKROCK CREEK 56.0
END DESCRIPTION:
XS GIS Cut Line= 3
      2911955.69     10152003.12      2912642.45     10152726.97
      2913055.71     10152953.13
#Sta/Elev= 30
  4002.2 1127.22  4037.6 1127.83  4072.8 1126.06  4256.8 1124.39  4359.5 1121.67
  4644.7 1116.18  4886.3 1112.41  4948.6 1112.65  4964.3 1110.80  4971.2 1107.66
  4985.3 1106.77  5027.7 1106.16  5066.0 1109.59  5081.7 1111.19  5094.9 1111.11
  5103.6 1107.92  5109.3 1109.26  5125.4 1106.18  5147.2 1105.54  5147.7 1105.04
  5158.6 1105.54  5193.6 1105.98  5234.4 1106.37  5268.3 1108.33  5316.0 1110.83
  5337.8 1113.10  5345.7 1115.40  5359.6 1114.68  5419.4 1120.31  5471.1 1127.09
#Mann=9,-1,0
  4002.2    0.05       0  4359.5    0.12       0  4644.7    0.05       0
  4948.6    0.12       0  5066.0    0.05       0  5147.2    0.07       0
  5158.6    0.05       0  5193.6    0.12       0  5268.3    0.05       0
Bank Sta=5147.2,5158.6
Exp/Cntr=0.3,0.1

Type RM Length L Ch R = 1,27500,500,500,500
BEGIN DESCRIPTION:
SLICKROCK CREEK 55.0
END DESCRIPTION:
XS GIS Cut Line= 3
      2911755.66     10152453.09      2912747.03     10153176.08
      2913155.73     10153253.12
#Sta/Elev= 30
  3773.0 1120.41  3830.6 1116.72  3885.1 1117.66  3935.5 1116.98  4152.7 1115.56
  4575.3 1107.74  4617.0 1108.24  4681.9 1105.90  4746.7 1107.38  4811.6 1106.99
  4853.4 1105.47  4947.2 1098.35  5012.4 1096.45  5029.2 1100.11  5049.5 1099.31
  5057.6 1096.43  5058.1 1095.93  5072.2 1096.43  5075.4 1096.54  5090.2 1096.95
  5110.6 1099.94  5117.3 1102.85  5181.8 1118.33  5273.4 1133.95  5284.8 1138.00
  5303.9 1140.31  5337.2 1146.41  5354.8 1151.73  5364.3 1152.42  5415.9 1157.78
#Mann=8,-1,0
  3773.0    0.05       0  3885.1    0.12       0  3935.5    0.05       0
  4947.2    0.12       0  5057.6    0.07       0  5072.2    0.12       0
  5075.4    0.05       0  5364.3    0.12       0
Bank Sta=5057.6,5072.2
Exp/Cntr=0.3,0.1

Type RM Length L Ch R = 1,27000,500,500,500
BEGIN DESCRIPTION:
SLICKROCK CREEK 54.0
END DESCRIPTION:
XS GIS Cut Line= 3
      2912205.69     10152903.13      2912590.86     10153613.64
      2913005.67     10153553.11
#Sta/Elev= 30
  4191.8 1110.30  4331.1 1106.72  4369.1 1105.01  4487.5 1103.20  4554.5 1099.81
  4669.6 1099.29  4680.0 1099.88  4723.8 1098.37  4767.5 1098.28  4817.4 1095.80
  4849.3 1095.15  4898.7 1097.54  4958.6 1096.09  4974.8 1095.49  4999.8 1089.01
  5007.6 1088.89  5008.1 1088.39  5022.3 1088.89  5034.2 1090.03  5039.3 1089.57
  5055.4 1091.76  5075.6 1092.98  5104.2 1094.10  5109.3 1093.26  5126.1 1095.99
  5179.3 1100.23  5217.1 1104.54  5375.4 1119.16  5399.0 1122.93  5419.2 1123.53
#Mann=4,-1,0
  4191.8    0.05       0  5007.6    0.05       0  5022.3    0.05       0
  5375.4    0.12       0
Bank Sta=5007.6,5022.3
Exp/Cntr=0.3,0.1

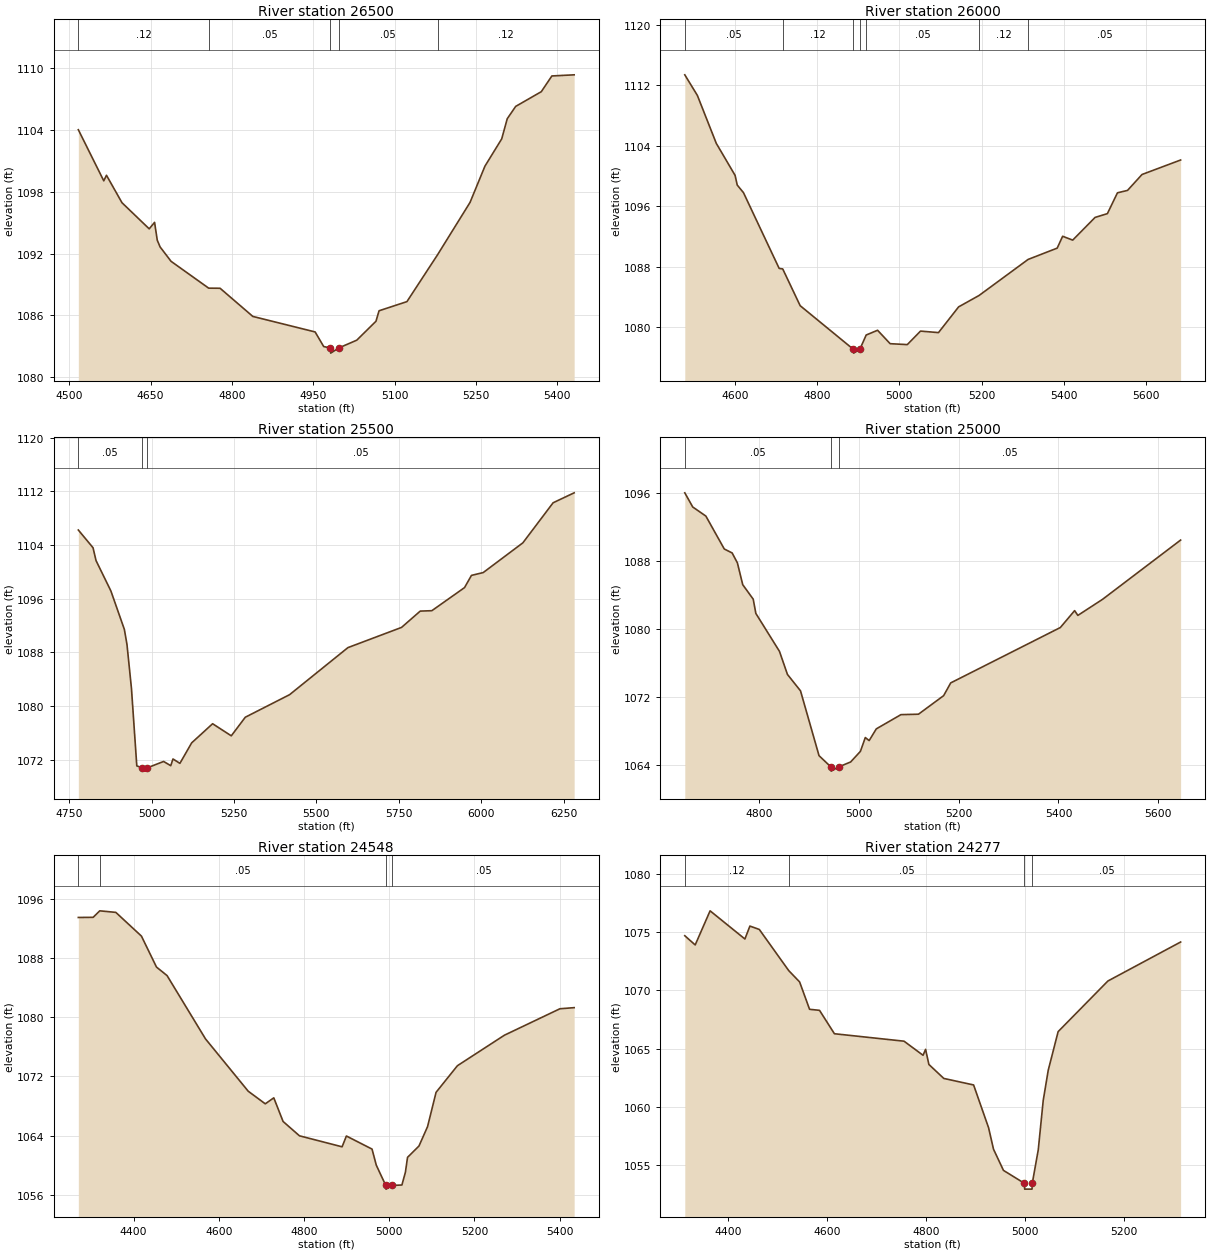
Type RM Length L Ch R = 1,26500,500,500,500
BEGIN DESCRIPTION:
SLICKROCK CREEK 53.0
END DESCRIPTION:
XS GIS Cut Line= 3
      2911755.64     10153903.11      2912236.16     10153952.98
      2912655.68     10154053.11
#Sta/Elev= 30
  4516.9 1104.04  4563.8 1099.07  4568.8 1099.61  4597.4 1096.94  4647.6 1094.40
  4657.5 1095.03  4662.5 1093.29  4667.7 1092.64  4687.9 1091.24  4757.3 1088.63
  4778.3 1088.62  4838.7 1085.88  4953.6 1084.37  4969.4 1082.95  4981.8 1082.81
  4982.3 1082.31  4997.1 1082.81  5030.4 1083.57  5065.8 1085.41  5071.5 1086.43
  5122.9 1087.32  5179.3 1091.87  5239.3 1096.97  5266.8 1100.50  5297.7 1103.15
  5307.9 1105.11  5323.5 1106.31  5370.7 1107.74  5390.2 1109.27  5431.3 1109.38
#Mann=5,-1,0
  4516.9    0.12       0  4757.3    0.05       0  4981.8    0.05       0
  4997.1    0.05       0  5179.3    0.12       0
Bank Sta=4981.8,4997.1
Exp/Cntr=0.3,0.1

Type RM Length L Ch R = 1,26000,500,500,500
BEGIN DESCRIPTION:
SLICKROCK CREEK 52.0
END DESCRIPTION:
XS GIS Cut Line= 3
      2911505.68     10154503.11      2912017.67     10154400.89
      2912655.65     10154153.12
#Sta/Elev= 30
  4477.9 1113.41  4508.5 1110.68  4554.5 1104.33  4600.3 1100.08  4605.5 1098.80
  4620.7 1097.79  4707.5 1087.75  4716.2 1087.68  4758.6 1082.81  4888.2 1077.02
  4888.7 1076.52  4903.8 1077.02  4919.3 1078.92  4947.0 1079.55  4977.6 1077.77
  5019.3 1077.65  5051.5 1079.44  5095.2 1079.24  5144.2 1082.65  5193.9 1084.16
  5313.3 1088.94  5384.1 1090.44  5397.3 1092.01  5421.8 1091.50  5476.3 1094.51
  5506.2 1095.01  5530.7 1097.77  5555.2 1098.09  5590.5 1100.20  5684.4 1102.12
#Mann=7,-1,0
  4477.9    0.05       0  4716.2    0.12       0  4888.2    0.05       0
  4903.8    0.12       0  4919.3    0.05       0  5193.9    0.12       0
  5313.3    0.05       0
Bank Sta=4888.2,4903.8
Exp/Cntr=0.3,0.1

Type RM Length L Ch R = 1,25500,500,500,500
BEGIN DESCRIPTION:
SLICKROCK CREEK 51.0
END DESCRIPTION:
XS GIS Cut Line= 3
      2911705.70     10154953.10      2911912.37     10154871.76
      2912855.66     10154003.14
#Sta/Elev= 30
  4777.9 1106.24  4822.5 1103.60  4831.6 1101.69  4876.7 1097.16  4917.6 1091.43
  4925.5 1089.19  4939.1 1082.64  4955.3 1071.10  4971.8 1070.82  4972.3 1070.32
  4987.5 1070.82  5036.7 1071.76  5058.3 1071.13  5065.1 1072.13  5086.1 1071.48
  5121.8 1074.53  5185.3 1077.38  5242.0 1075.58  5284.5 1078.35  5418.9 1081.71
  5595.9 1088.72  5758.6 1091.73  5815.3 1094.16  5850.5 1094.22  5949.7 1097.66
  5970.7 1099.48  6006.4 1099.90  6126.7 1104.33  6218.5 1110.30  6282.3 1111.78
#Mann=3,-1,0
  4777.9    0.05       0  4971.8    0.05       0  4987.5    0.05       0
Bank Sta=4971.8,4987.5
Exp/Cntr=0.3,0.1

Type RM Length L Ch R = 1,25000,452,452,452
BEGIN DESCRIPTION:
SLICKROCK CREEK 50.0
END DESCRIPTION:
XS GIS Cut Line= 3
      2911905.65     10155353.12      2912236.50     10155243.01
      2912655.71     10154753.08
#Sta/Elev= 30
  4651.3 1096.03  4667.2 1094.36  4693.5 1093.29  4730.4 1089.41  4746.2 1088.94
  4756.7 1087.77  4767.4 1085.20  4788.4 1083.49  4793.7 1081.81  4841.0 1077.34
  4857.0 1074.62  4883.2 1072.68  4920.3 1065.04  4944.0 1063.72  4944.5 1063.22
  4959.8 1063.72  4983.6 1064.30  5003.2 1065.55  5013.0 1067.18  5020.7 1066.82
  5035.0 1068.20  5084.4 1069.88  5119.5 1069.93  5170.0 1072.12  5184.1 1073.62
  5403.8 1080.15  5432.4 1082.14  5438.9 1081.58  5488.3 1083.47  5644.8 1090.46
#Mann=3,-1,0
  4651.3    0.05       0  4944.0    0.05       0  4959.8    0.05       0
Bank Sta=4944,4959.8
Exp/Cntr=0.3,0.1

Type RM Length L Ch R = 1,24548,271,271,271
BEGIN DESCRIPTION:
Mapping XS 9fa0626a
END DESCRIPTION:
XS GIS Cut Line= 2
      2911837.91     10155600.61      2912999.01     10155521.35
#Sta/Elev= 30
  4270.3 1093.52  4305.1 1093.54  4320.6 1094.42  4358.3 1094.21  4418.4 1091.00
  4453.7 1086.81  4478.6 1085.65  4568.8 1077.08  4669.0 1070.00  4709.1 1068.29
  4729.1 1069.10  4750.9 1065.90  4789.3 1063.96  4889.4 1062.47  4899.5 1063.93
  4959.7 1062.16  4969.7 1059.98  4991.9 1057.24  4992.4 1056.74  5007.7 1057.24
  5029.8 1057.30  5038.0 1059.02  5043.0 1061.04  5069.9 1062.58  5090.0 1065.20
  5110.0 1069.85  5160.1 1073.45  5270.4 1077.58  5400.7 1081.16  5434.1 1081.31
#Mann=4,-1,0
  4270.3    0.12       0  4320.6    0.05       0  4991.9    0.05       0
  5007.7    0.05       0
Bank Sta=4991.9,5007.7
Exp/Cntr=0.3,0.1

Type RM Length L Ch R = 1,24277,487,487,487
BEGIN DESCRIPTION:
Mapping XS 02e05f05
END DESCRIPTION:
XS GIS Cut Line= 2
      2911964.76     10155862.16      2912962.01     10155771.14
#Sta/Elev= 30
  4313.0 1074.69  4334.0 1073.90  4364.1 1076.83  4434.4 1074.41  4444.5 1075.52
  4463.5 1075.23  4522.8 1071.70  4544.9 1070.72  4565.0 1068.37  4585.1 1068.28
  4615.2 1066.27  4755.8 1065.63  4794.2 1064.42  4799.3 1064.93  4806.0 1063.63
  4836.1 1062.43  4896.3 1061.87  4926.5 1058.20  4936.5 1056.35  4956.6 1054.53
  4998.9 1053.42  4999.4 1052.92  5014.3 1052.92  5014.8 1053.42  5026.9 1056.30
  5036.9 1060.54  5047.0 1063.13  5067.0 1066.45  5167.5 1070.80  5314.4 1074.15
#Mann=4,-1,0
  4313.0    0.12       0  4522.8    0.05       0  4998.9    0.05       0
  5014.8    0.05       0
Bank Sta=4998.9,5014.8
Exp/Cntr=0.3,0.1

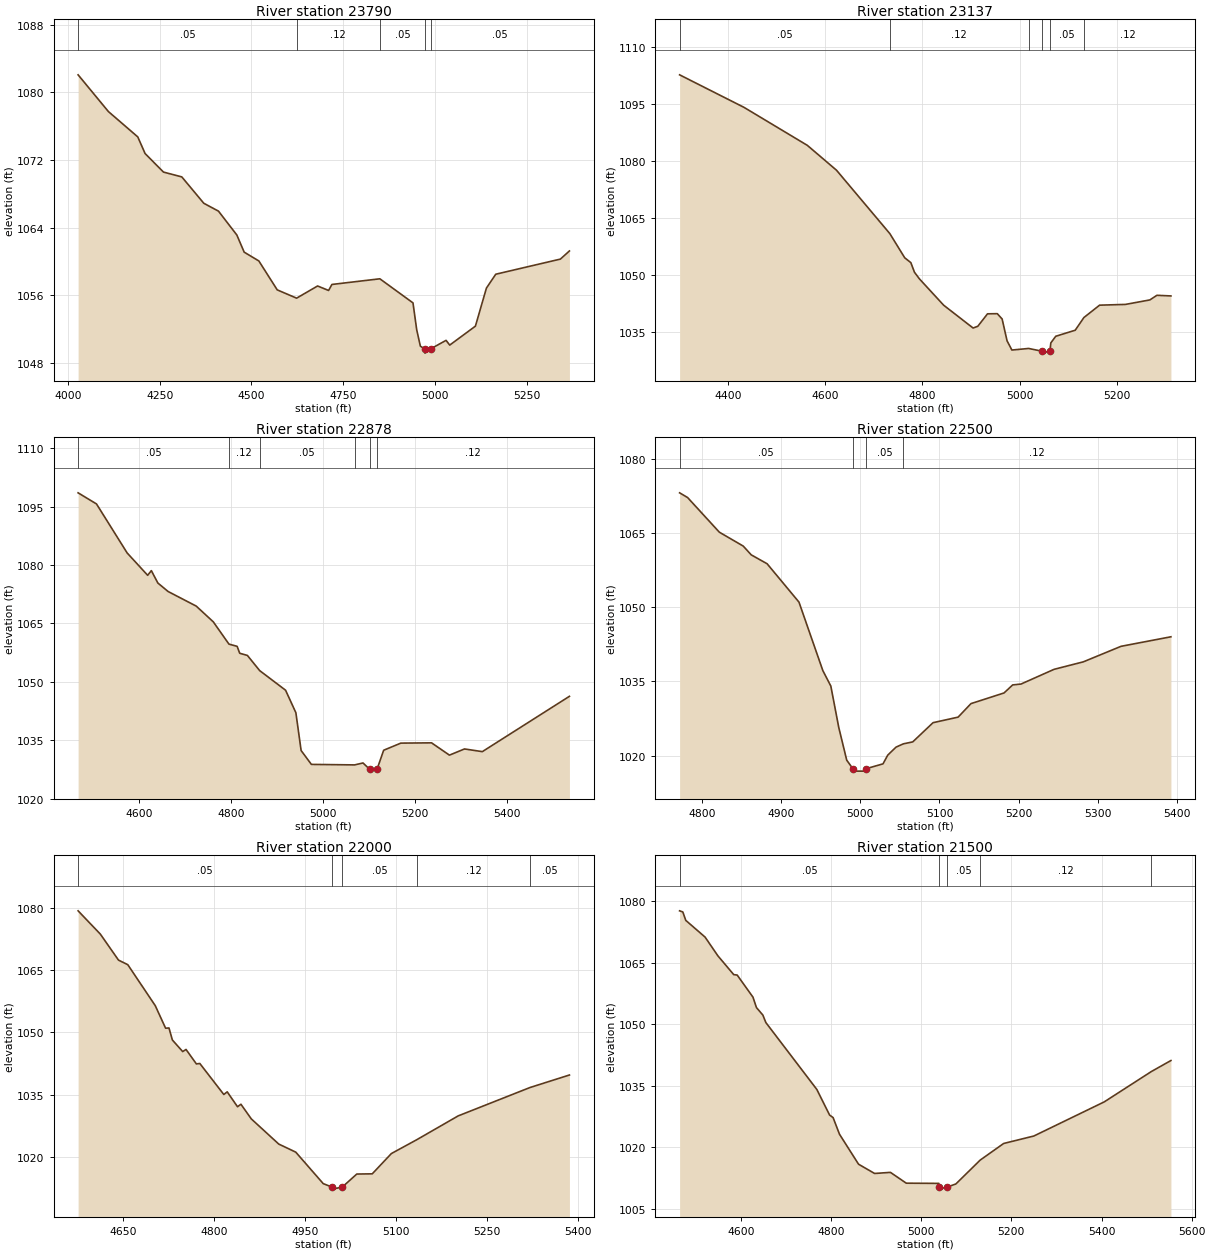
Type RM Length L Ch R = 1,23790,653,653,653
BEGIN DESCRIPTION:
Mapping XS c21e6224
END DESCRIPTION:
XS GIS Cut Line= 3
      2911703.17     10156262.41      2912931.66     10156290.15
      2912999.04     10156202.96
#Sta/Elev= 30
  4027.8 1082.06  4110.3 1077.72  4190.4 1074.72  4210.4 1072.75  4260.4 1070.56
  4310.4 1069.99  4370.4 1066.87  4410.4 1065.94  4460.4 1063.12  4480.4 1061.09
  4520.4 1060.05  4570.5 1056.63  4623.3 1055.65  4680.5 1057.09  4710.5 1056.56
  4719.5 1057.27  4850.2 1057.94  4940.5 1055.09  4950.6 1051.91  4960.6 1049.97
  4972.6 1049.65  4973.1 1049.15  4988.5 1049.65  5030.6 1050.66  5040.6 1050.10
  5110.6 1052.34  5140.6 1056.84  5166.0 1058.48  5342.2 1060.27  5366.8 1061.23
#Mann=5,-1,0
  4027.8    0.05       0  4623.3    0.12       0  4850.2    0.05       0
  4972.6    0.05       0  4988.5    0.05       0
Bank Sta=4972.6,4988.5
Exp/Cntr=0.3,0.1

Type RM Length L Ch R = 1,23137,259,259,259
BEGIN DESCRIPTION:
Mapping XS f9348529
END DESCRIPTION:
XS GIS Cut Line= 3
      2911873.56     10156975.72      2912769.19     10156904.39
      2912836.55     10156813.25
#Sta/Elev= 30
  4300.0 1102.70  4432.5 1094.14  4563.0 1084.13  4623.1 1077.58  4732.9 1060.89
  4763.6 1054.52  4776.2 1053.24  4783.7 1050.71  4793.7 1048.99  4843.8 1042.03
  4904.4 1036.02  4914.1 1036.48  4934.1 1039.76  4954.2 1039.80  4964.2 1038.40
  4974.3 1032.67  4984.3 1030.22  5018.8 1030.64  5046.6 1029.91  5047.1 1029.41
  5062.5 1029.91  5064.5 1032.10  5074.6 1033.85  5114.7 1035.44  5132.6 1038.78
  5164.9 1042.04  5218.3 1042.24  5268.4 1043.42  5283.0 1044.64  5311.8 1044.47
#Mann=6,-1,0
  4300.0    0.05       0  4732.9    0.12       0  5018.8    0.05       0
  5046.6    0.07       0  5062.5    0.05       0  5132.6    0.12       0
Bank Sta=5046.6,5062.5
Exp/Cntr=0.3,0.1

Type RM Length L Ch R = 1,22878,378,378,378
BEGIN DESCRIPTION:
Mapping XS a52c35eb
END DESCRIPTION:
XS GIS Cut Line= 3
      2912143.83     10157415.63      2912893.79     10157033.70
      2913011.28     10156840.19
#Sta/Elev= 30
  4468.3 1098.58  4508.3 1095.72  4575.0 1083.11  4619.5 1077.38  4627.5 1078.58
  4641.7 1075.39  4664.0 1073.21  4725.1 1069.46  4762.2 1065.41  4796.2 1059.69
  4814.0 1059.12  4819.6 1057.34  4836.3 1056.78  4863.0 1052.88  4919.3 1047.84
  4941.7 1042.05  4953.1 1032.33  4975.4 1028.77  5069.5 1028.64  5087.6 1029.14
  5101.9 1027.54  5102.4 1027.04  5118.2 1027.54  5132.5 1032.41  5169.9 1034.24
  5236.6 1034.31  5275.5 1031.15  5308.2 1032.74  5347.0 1032.05  5536.3 1046.27
#Mann=6,-1,0
  4468.3    0.05       0  4796.2    0.12       0  4863.0    0.05       0
  5069.5    0.12       0  5101.9    0.05       0  5118.2    0.12       0
Bank Sta=5101.9,5118.2
Exp/Cntr=0.3,0.1

Type RM Length L Ch R = 1,22500,500,500,500
BEGIN DESCRIPTION:
SLICKROCK CREEK 45.0
END DESCRIPTION:
XS GIS Cut Line= 3
      2912905.68     10157603.11      2912931.92     10157375.92
      2913055.68     10157003.13
#Sta/Elev= 30
  4771.3 1073.08  4781.4 1072.13  4821.6 1065.13  4851.8 1062.33  4861.9 1060.56
  4882.0 1058.76  4922.3 1051.02  4952.5 1037.19  4962.6 1034.07  4972.6 1025.74
  4982.7 1019.11  4990.4 1017.40  4990.9 1016.90  5006.9 1016.90  5007.4 1017.40
  5028.6 1018.37  5034.6 1020.13  5045.1 1021.75  5054.4 1022.41  5066.2 1022.80
  5091.9 1026.68  5123.6 1027.80  5139.9 1030.53  5181.7 1032.68  5192.6 1034.30
  5203.2 1034.48  5245.0 1037.45  5282.0 1038.96  5329.6 1042.09  5392.8 1044.02
#Mann=4,-1,0
  4771.3    0.05       0  4990.4    0.05       0  5007.4    0.05       0
  5054.4    0.12       0
Bank Sta=4990.4,5007.4
Exp/Cntr=0.3,0.1

Type RM Length L Ch R = 1,22000,500,500,500
BEGIN DESCRIPTION:
SLICKROCK CREEK 44.0
END DESCRIPTION:
XS GIS Cut Line= 3
      2913205.68     10157953.12      2913389.89     10157571.12
      2913505.69     10157203.11
#Sta/Elev= 30
  4575.9 1079.27  4612.6 1073.66  4642.5 1067.41  4657.8 1066.31  4703.1 1056.45
  4720.1 1051.03  4725.7 1051.08  4731.3 1048.19  4748.3 1045.40  4753.8 1045.91
  4770.9 1042.43  4776.5 1042.54  4816.1 1035.07  4821.7 1035.71  4838.7 1032.12
  4844.3 1032.73  4861.4 1029.20  4906.6 1023.15  4934.7 1021.20  4980.0 1013.62
  4994.4 1012.80  4994.9 1012.30  5011.4 1012.80  5035.3 1015.93  5060.8 1015.98
  5092.3 1020.86  5134.3 1024.20  5202.4 1029.92  5320.8 1036.75  5385.8 1039.76
#Mann=5,-1,0
  4575.9    0.05       0  4994.4    0.03       0  5011.4    0.05       0
  5134.3    0.12       0  5320.8    0.05       0
Bank Sta=4994.4,5011.4
Exp/Cntr=0.3,0.1

Type RM Length L Ch R = 1,21500,500,500,500
BEGIN DESCRIPTION:
SLICKROCK CREEK 43.0
END DESCRIPTION:
XS GIS Cut Line= 3
      2913505.70     10158153.10      2913856.76     10157748.06
      2914105.67     10157253.13
#Sta/Elev= 30
  4464.0 1077.64  4471.1 1077.37  4477.7 1075.31  4520.5 1071.23  4549.0 1066.65
  4584.1 1062.07  4591.7 1061.97  4626.8 1056.57  4634.5 1054.03  4648.7 1052.20
  4655.4 1050.37  4768.4 1034.06  4796.8 1027.80  4804.5 1027.19  4818.7 1023.13
  4861.0 1015.81  4896.6 1013.55  4931.7 1013.82  4966.9 1011.18  5039.1 1011.13
  5040.4 1010.23  5040.9 1009.73  5057.5 1010.23  5076.9 1010.99  5130.8 1016.81
  5182.9 1020.87  5249.9 1022.69  5406.1 1031.02  5510.4 1038.41  5554.0 1041.11
#Mann=5,-1,0
  4464.0    0.05       0  5040.4    0.05       0  5057.5    0.05       0
  5130.8    0.12       0  5510.4    0.05       0
Bank Sta=5040.4,5057.5
Exp/Cntr=0.3,0.1

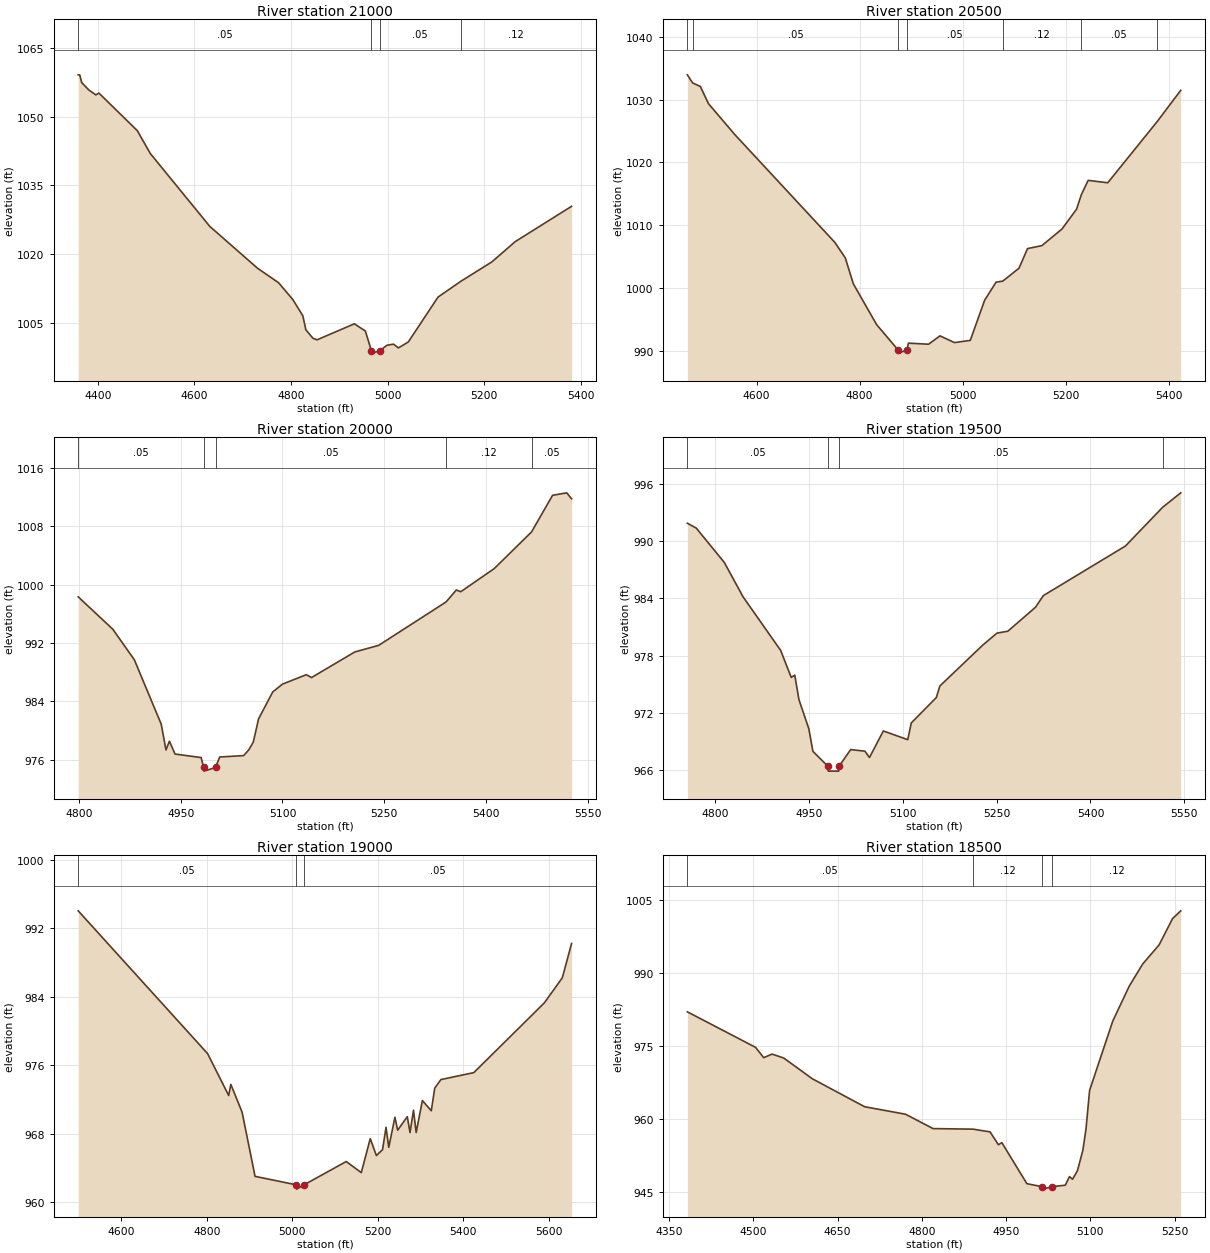
Type RM Length L Ch R = 1,21000,500,500,500
BEGIN DESCRIPTION:
SLICKROCK CREEK 42.0
END DESCRIPTION:
XS GIS Cut Line= 3
      2913805.69     10158303.11      2914322.92     10157924.99
      2914405.69     10157553.09
#Sta/Elev= 30
  4359.3 1059.17  4362.4 1059.17  4366.6 1057.47  4381.3 1055.86  4396.0 1054.78
  4402.1 1055.19  4481.7 1046.97  4508.7 1041.96  4631.8 1026.05  4730.9 1016.89
  4774.3 1013.74  4803.7 1010.07  4824.5 1006.51  4830.7 1003.46  4845.4 1001.61
  4853.9 1001.27  4931.1 1004.76  4953.9 1003.20  4966.5  998.86  4967.0  998.36
  4983.7  998.86  4998.6 1000.08  5012.2 1000.32  5022.4  999.50  5042.9 1000.80
  5104.4 1010.60  5151.4 1014.04  5215.9 1018.29  5264.5 1022.74  5381.0 1030.44
#Mann=4,-1,0
  4359.3    0.05       0  4966.5    0.05       0  4983.7    0.05       0
  5151.4    0.12       0
Bank Sta=4966.5,4983.7
Exp/Cntr=0.3,0.1

Type RM Length L Ch R = 1,20500,500,500,500
BEGIN DESCRIPTION:
SLICKROCK CREEK 41.0
END DESCRIPTION:
XS GIS Cut Line= 3
      2914105.65     10158403.12      2914628.98     10158295.38
      2915005.65     10158103.13
#Sta/Elev= 30
  4465.7 1033.97  4475.9 1032.68  4490.9 1032.11  4506.6 1029.38  4557.6 1024.46
  4751.6 1007.29  4772.0 1004.81  4787.7 1000.66  4832.9  994.16  4874.6  990.12
  4875.1  989.62  4892.0  990.12  4894.5  991.21  4933.6  991.04  4955.8  992.37
  4983.9  991.30  5014.6  991.65  5042.4  998.04  5064.6 1000.93  5077.5 1001.09
  5109.1 1003.15  5125.7 1006.28  5153.5 1006.75  5192.4 1009.39  5220.8 1012.56
  5230.1 1014.88  5243.3 1017.15  5281.3 1016.77  5376.8 1026.48  5422.9 1031.50
#Mann=7,-1,0
  4465.7    0.12       0  4475.9    0.05       0  4874.6    0.05       0
  4892.0    0.05       0  5077.5    0.12       0  5230.1    0.05       0
  5376.8    0.12       0
Bank Sta=4874.6,4892
Exp/Cntr=0.3,0.1

Type RM Length L Ch R = 1,20000,500,500,500
BEGIN DESCRIPTION:
SLICKROCK CREEK 40.0
END DESCRIPTION:
XS GIS Cut Line= 3
      2914405.65     10158753.11      2914602.88     10158791.36
      2915005.69     10158453.10
#Sta/Elev= 30
  4799.1  998.34  4850.1  993.89  4881.8  989.70  4921.4  980.86  4928.4  977.32
  4933.5  978.52  4941.7  976.76  4980.2  976.27  4984.0  974.91  4984.5  974.41
  5001.4  974.91  5007.6  976.35  5042.8  976.54  5050.5  977.34  5057.1  978.40
  5064.8  981.58  5085.7  985.28  5100.0  986.35  5135.1  987.65  5142.9  987.26
  5206.6  990.77  5241.8  991.68  5341.0  997.63  5356.2  999.28  5362.7  999.04
  5412.2 1002.23  5467.0 1007.25  5498.0 1012.28  5518.8 1012.62  5526.0 1011.80
#Mann=5,-1,0
  4799.1    0.05       0  4984.0    0.03       0  5001.4    0.05       0
  5341.0    0.12       0  5467.0    0.05       0
Bank Sta=4984,5001.4
Exp/Cntr=0.3,0.1

Type RM Length L Ch R = 1,19500,500,500,500
BEGIN DESCRIPTION:
SLICKROCK CREEK 39.0
END DESCRIPTION:
XS GIS Cut Line= 3
      2914555.66     10159353.12      2914774.55     10159245.77
      2915005.69     10158753.10
#Sta/Elev= 30
  4756.2  991.87  4770.3  991.37  4815.2  987.76  4845.3  984.14  4905.2  978.54
  4922.1  975.70  4927.7  975.95  4934.4  973.38  4950.2  970.32  4956.7  967.96
  4980.8  966.38  4981.3  965.88  4997.9  965.88  4998.4  966.38  5017.0  968.14
  5039.8  967.97  5047.1  967.31  5069.2  970.09  5108.2  969.18  5113.8  970.93
  5153.9  973.60  5159.4  974.80  5227.9  979.09  5250.7  980.35  5268.0  980.55
  5312.2  983.06  5324.7  984.28  5455.8  989.48  5515.4  993.55  5544.2  995.06
#Mann=4,-1,0
  4756.2    0.05       0  4980.8    0.03       0  4998.4    0.05       0
  5515.4    0.12       0
Bank Sta=4980.8,4998.4
Exp/Cntr=0.3,0.1

Type RM Length L Ch R = 1,19000,500,500,500
BEGIN DESCRIPTION:
SLICKROCK CREEK 38.0
END DESCRIPTION:
XS GIS Cut Line= 3
      2914605.65     10159553.11      2915102.03     10159616.42
      2915505.68     10159103.12
#Sta/Elev= 30
  4499.6  994.05  4802.1  977.38  4851.4  972.49  4856.4  973.79  4882.7  970.55
  4913.0  963.05  5009.7  962.06  5010.2  961.56  5027.5  962.06  5126.2  964.78
  5161.4  963.49  5182.3  967.45  5196.7  965.48  5211.1  966.17  5219.2  968.78
  5225.6  966.44  5240.0  969.95  5246.4  968.44  5268.9  970.02  5275.3  968.17
  5283.4  970.77  5289.7  968.17  5304.2  971.90  5325.0  970.71  5333.1  973.35
  5347.5  974.35  5424.4  975.16  5589.4  983.31  5631.3  986.23  5653.0  990.24
#Mann=3,-1,0
  4499.6    0.05       0  5009.7    0.03       0  5027.5    0.05       0
Bank Sta=5009.7,5027.5
Exp/Cntr=0.3,0.1

Type RM Length L Ch R = 1,18500,500,500,500
BEGIN DESCRIPTION:
SLICKROCK CREEK 37.0
END DESCRIPTION:
XS GIS Cut Line= 3
      2914755.65     10159703.09      2915264.46     10160053.32
      2915505.64     10160153.09
#Sta/Elev= 30
  4382.3  982.04  4503.7  974.74  4518.3  972.61  4533.2  973.35  4554.1  972.53
  4604.9  968.27  4698.0  962.52  4770.8  960.98  4819.9  958.02  4890.7  957.91
  4921.4  957.35  4936.3  954.70  4942.4  955.13  4987.0  946.69  5014.0  946.07
  5014.5  945.57  5032.0  946.07  5055.4  946.38  5062.8  948.14  5068.3  947.61
  5077.1  949.38  5086.7  953.57  5092.2  957.88  5098.7  965.89  5140.0  980.16
  5169.3  987.33  5193.2  991.87  5222.5  995.82  5246.4 1001.22  5261.0 1002.82
#Mann=4,-1,0
  4382.3    0.05       0  4890.7    0.12       0  5014.0    0.07       0
  5032.0    0.12       0
Bank Sta=5014,5032
Exp/Cntr=0.3,0.1