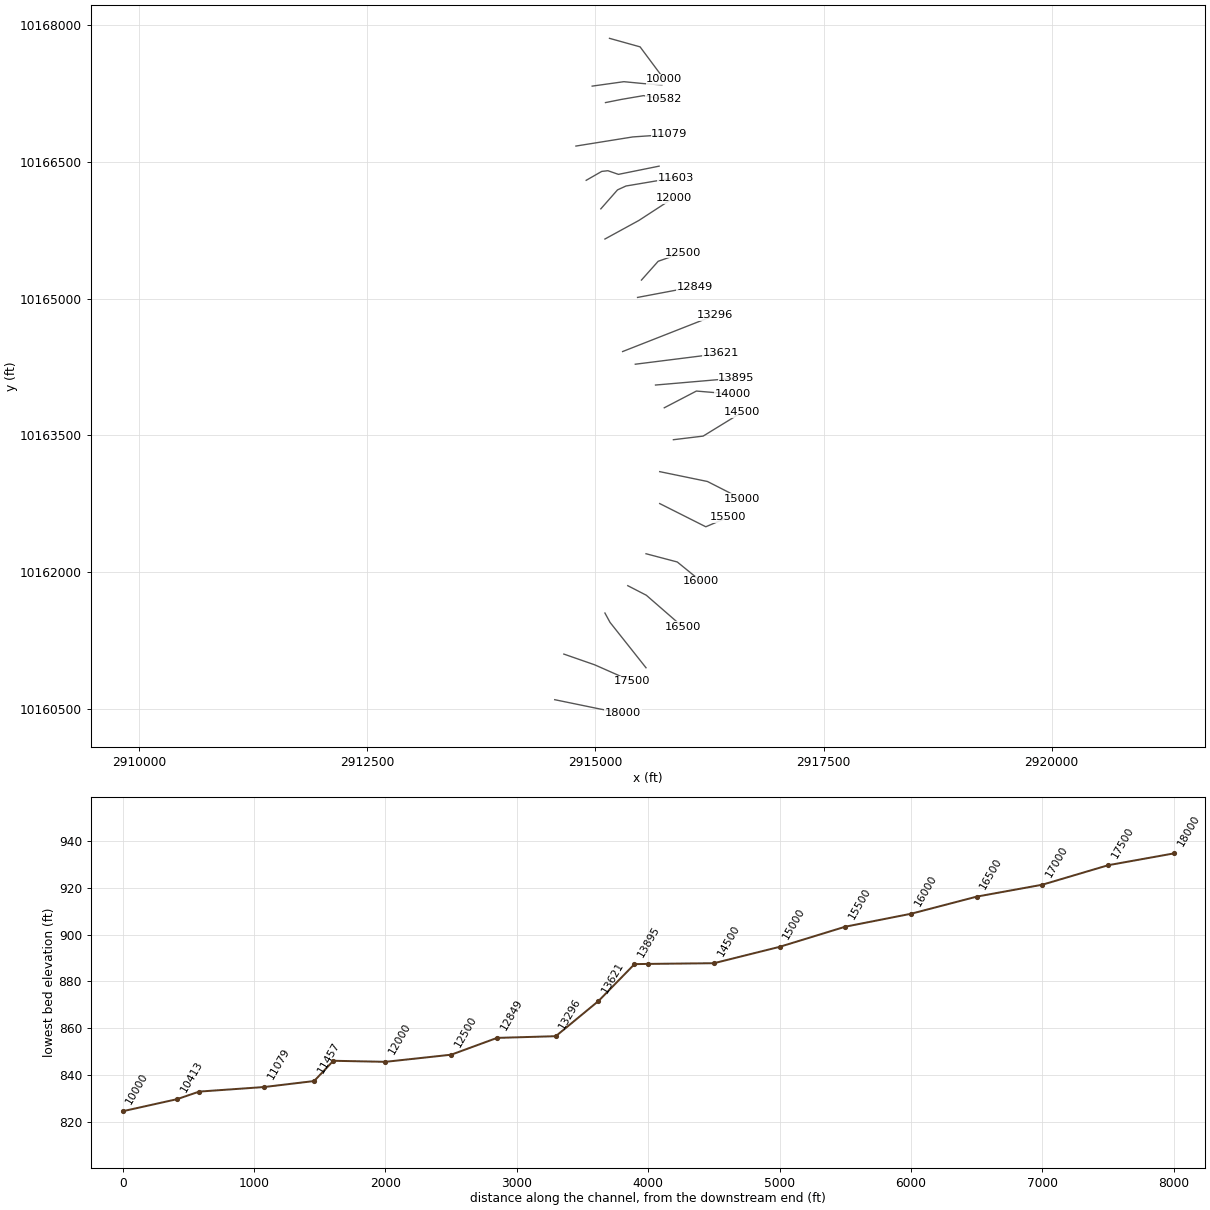
HEC-RAS study SLICKROCK CREEK.prj: SLICKROCK CREEK Base Level Engineering

--- SLICKROCK CREEK.g01 (geometry) --- (continued)

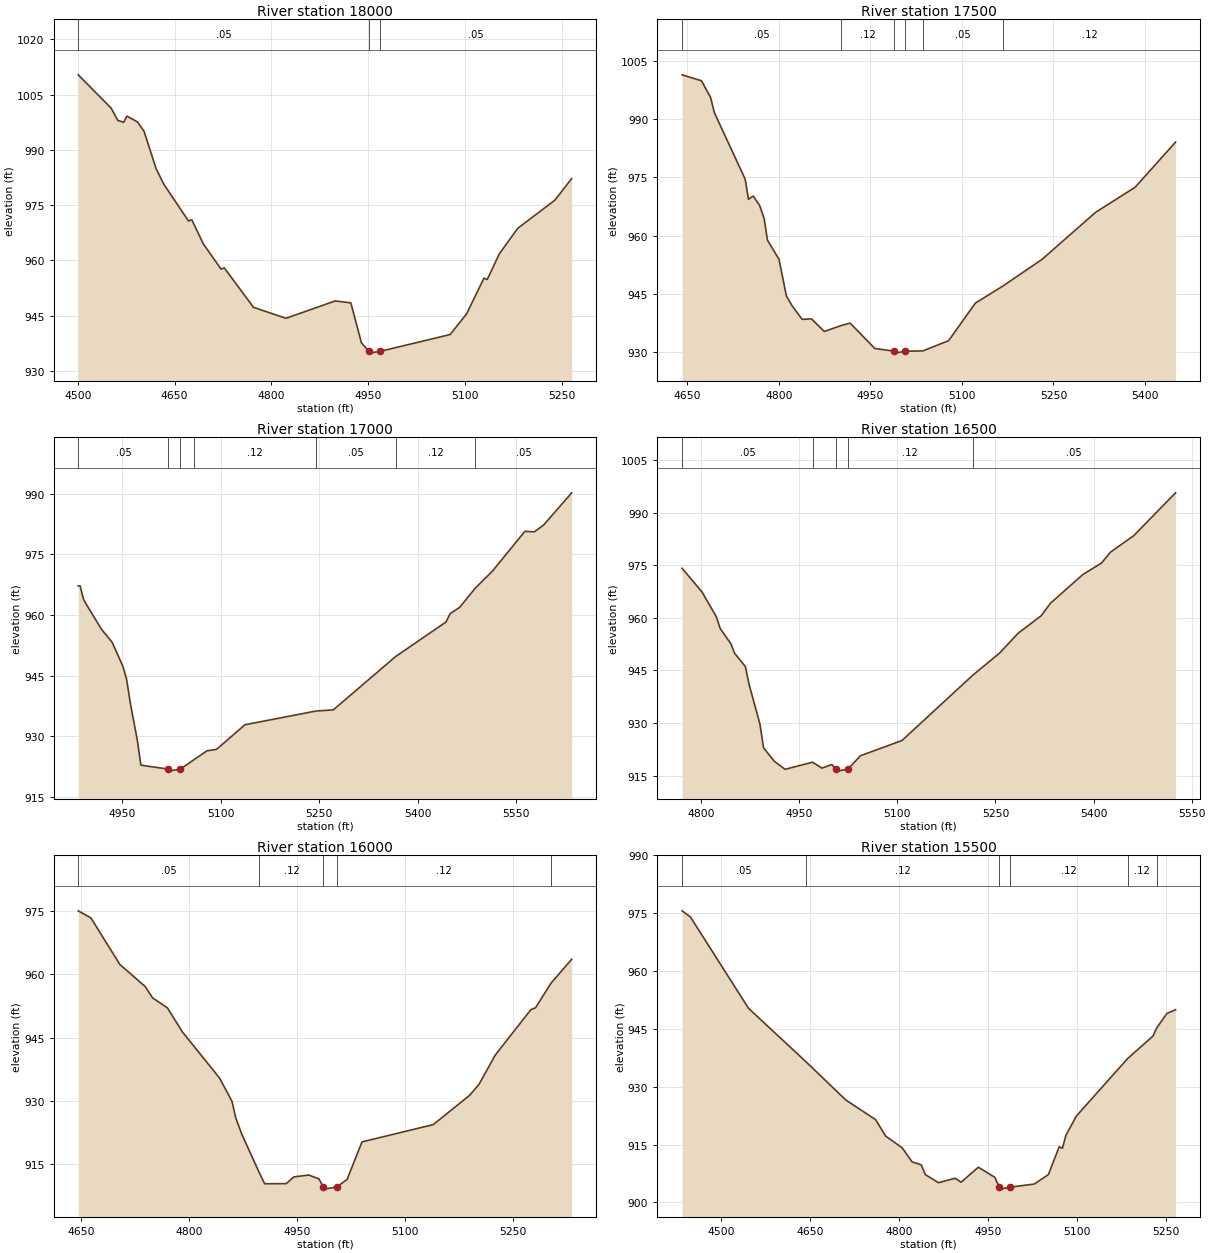
Type RM Length L Ch R = 1,18000,500,500,500
BEGIN DESCRIPTION:
SLICKROCK CREEK 36.0
END DESCRIPTION:
XS GIS Cut Line= 3
      2914555.66     10160603.12      2915044.90     10160502.39
      2915305.68     10160453.11
#Sta/Elev= 30
  4500.5 1010.39  4551.6 1001.34  4561.8  998.02  4570.9  997.49  4576.0  999.17
  4592.4  997.59  4602.6  995.04  4621.2  984.91  4633.3  980.64  4671.5  970.67
  4676.6  971.03  4694.5  964.45  4721.9  957.62  4727.0  957.93  4772.2  947.24
  4822.5  944.25  4898.7  948.96  4923.1  948.45  4939.5  937.59  4950.9  935.29
  4951.4  934.79  4969.0  935.29  5077.0  939.84  5102.6  945.47  5129.4  955.16
  5134.5  954.80  5153.5  961.84  5181.8  968.70  5239.2  976.32  5265.4  982.20
#Mann=3,-1,0
  4500.5    0.05       0  4950.9    0.03       0  4969.0    0.05       0
Bank Sta=4950.9,4969
Exp/Cntr=0.3,0.1

Type RM Length L Ch R = 1,17500,500,500,500
BEGIN DESCRIPTION:
SLICKROCK CREEK 35.0
END DESCRIPTION:
XS GIS Cut Line= 3
      2914655.72     10161103.10      2914994.06     10160985.18
      2915405.69     10160803.11
#Sta/Elev= 30
  4641.7 1001.35  4673.4  999.82  4688.3  995.57  4694.6  991.61  4745.1  974.49
  4750.4  969.30  4758.2  970.17  4768.7  967.75  4776.2  964.33  4781.5  958.83
  4800.5  953.87  4812.6  944.42  4821.7  941.97  4838.4  938.43  4853.5  938.56
  4874.7  935.31  4902.5  936.84  4917.0  937.47  4957.4  930.94  4989.2  930.24
  4989.7  929.74  5007.3  930.24  5036.2  930.31  5078.3  932.95  5122.1  942.60
  5168.0  947.08  5231.4  953.87  5319.2  965.98  5383.7  972.40  5450.1  984.04
#Mann=6,-1,0
  4641.7    0.05       0  4902.5    0.12       0  4989.2    0.07       0
  5007.3    0.12       0  5036.2    0.05       0  5168.0    0.12       0
Bank Sta=4989.2,5007.3
Exp/Cntr=0.3,0.1

Type RM Length L Ch R = 1,17000,500,500,500
BEGIN DESCRIPTION:
SLICKROCK CREEK 34.0
END DESCRIPTION:
XS GIS Cut Line= 3
      2915105.67     10161553.13      2915161.49     10161450.65
      2915555.70     10160953.09
#Sta/Elev= 30
  4883.3  967.23  4886.2  967.23  4891.4  963.90  4897.1  962.26  4918.9  956.46
  4935.1  953.25  4951.2  947.39  4956.9  944.23  4963.0  937.89  4973.1  929.29
  4978.8  922.88  5020.7  921.91  5021.2  921.41  5038.9  921.91  5060.2  924.31
  5079.5  926.44  5093.9  926.78  5137.2  932.88  5245.4  936.27  5271.8  936.56
  5366.7  949.75  5443.3  958.28  5449.7  960.35  5464.1  961.90  5488.0  966.67
  5513.8  970.82  5563.5  980.72  5577.9  980.58  5592.3  982.32  5634.8  990.24
#Mann=7,-1,0
  4883.3    0.05       0  5020.7    0.03       0  5038.9    0.05       0
  5060.2    0.12       0  5245.4    0.05       0  5366.7    0.12       0
  5488.0    0.05       0
Bank Sta=5020.7,5038.9
Exp/Cntr=0.3,0.1

Type RM Length L Ch R = 1,16500,500,500,500
BEGIN DESCRIPTION:
SLICKROCK CREEK 33.0
END DESCRIPTION:
XS GIS Cut Line= 3
      2915355.72     10161853.09      2915559.30     10161748.00
      2915955.67     10161403.13
#Sta/Elev= 30
  4770.9  974.13  4801.3  967.40  4823.4  960.27  4829.1  956.99  4845.6  952.58
  4851.2  949.89  4867.7  946.11  4873.4  940.97  4889.9  929.76  4895.5  922.92
  4912.0  919.09  4928.4  916.82  4970.4  918.85  4984.7  917.15  4999.9  918.19
  5006.0  916.80  5006.5  916.30  5024.2  916.80  5043.6  920.68  5107.2  925.04
  5215.0  943.59  5256.3  949.95  5284.7  955.61  5319.9  960.59  5334.1  964.15
  5383.5  972.33  5412.0  975.60  5426.2  978.77  5461.3  983.40  5525.4  995.64
#Mann=5,-1,0
  4770.9    0.05       0  4970.4    0.12       0  5006.0    0.07       0
  5024.2    0.12       0  5215.0    0.05       0
Bank Sta=5006,5024.2
Exp/Cntr=0.3,0.1

Type RM Length L Ch R = 1,16000,500,500,500
BEGIN DESCRIPTION:
SLICKROCK CREEK 32.0
END DESCRIPTION:
XS GIS Cut Line= 3
      2915555.69     10162203.11      2915898.09     10162112.83
      2916155.70     10161903.10
#Sta/Elev= 30
  4645.9  975.13  4663.5  973.46  4703.8  962.38  4738.9  957.16  4749.3  954.44
  4770.0  952.06  4790.7  946.36  4842.4  935.40  4859.8  929.83  4864.9  925.97
  4873.4  922.02  4897.9  912.82  4905.2  910.24  4935.2  910.28  4945.8  911.87
  4966.5  912.33  4980.6  911.41  4987.0  909.47  4987.5  908.97  5005.3  909.47
  5019.8  911.26  5040.6  920.20  5139.7  924.31  5190.3  931.28  5203.6  933.96
  5225.9  940.84  5275.4  951.63  5281.9  952.08  5303.4  957.92  5332.2  963.61
#Mann=5,-1,0
  4645.9    0.05       0  4897.9    0.12       0  4987.0    0.07       0
  5005.3    0.12       0  5303.4    0.05       0
Bank Sta=4987,5005.3
Exp/Cntr=0.3,0.1

Type RM Length L Ch R = 1,15500,500,500,500
BEGIN DESCRIPTION:
SLICKROCK CREEK 31.0
END DESCRIPTION:
XS GIS Cut Line= 3
      2915705.65     10162753.13      2916210.80     10162498.70
      2916455.67     10162603.11
#Sta/Elev= 30
  4434.4  975.64  4448.4  974.06  4546.4  950.35  4643.6  936.43  4710.5  926.55
  4760.8  921.44  4777.5  917.20  4805.4  914.16  4822.1  910.50  4837.5  909.75
  4844.4  907.21  4866.7  905.10  4894.6  906.27  4904.7  905.23  4933.7  909.12
  4961.6  906.50  4969.1  903.94  4969.6  903.44  4987.5  903.94  5028.2  904.77
  5051.9  907.22  5070.0  914.42  5075.5  914.04  5081.4  917.40  5099.1  922.42
  5185.3  937.30  5228.1  943.14  5234.4  945.25  5251.7  949.03  5266.2  949.98
#Mann=6,-1,0
  4434.4    0.05       0  4643.6    0.12       0  4969.1    0.03       0
  4987.5    0.12       0  5185.3    0.12       0  5234.4    0.05       0
Bank Sta=4969.1,4987.5
Exp/Cntr=0.3,0.1

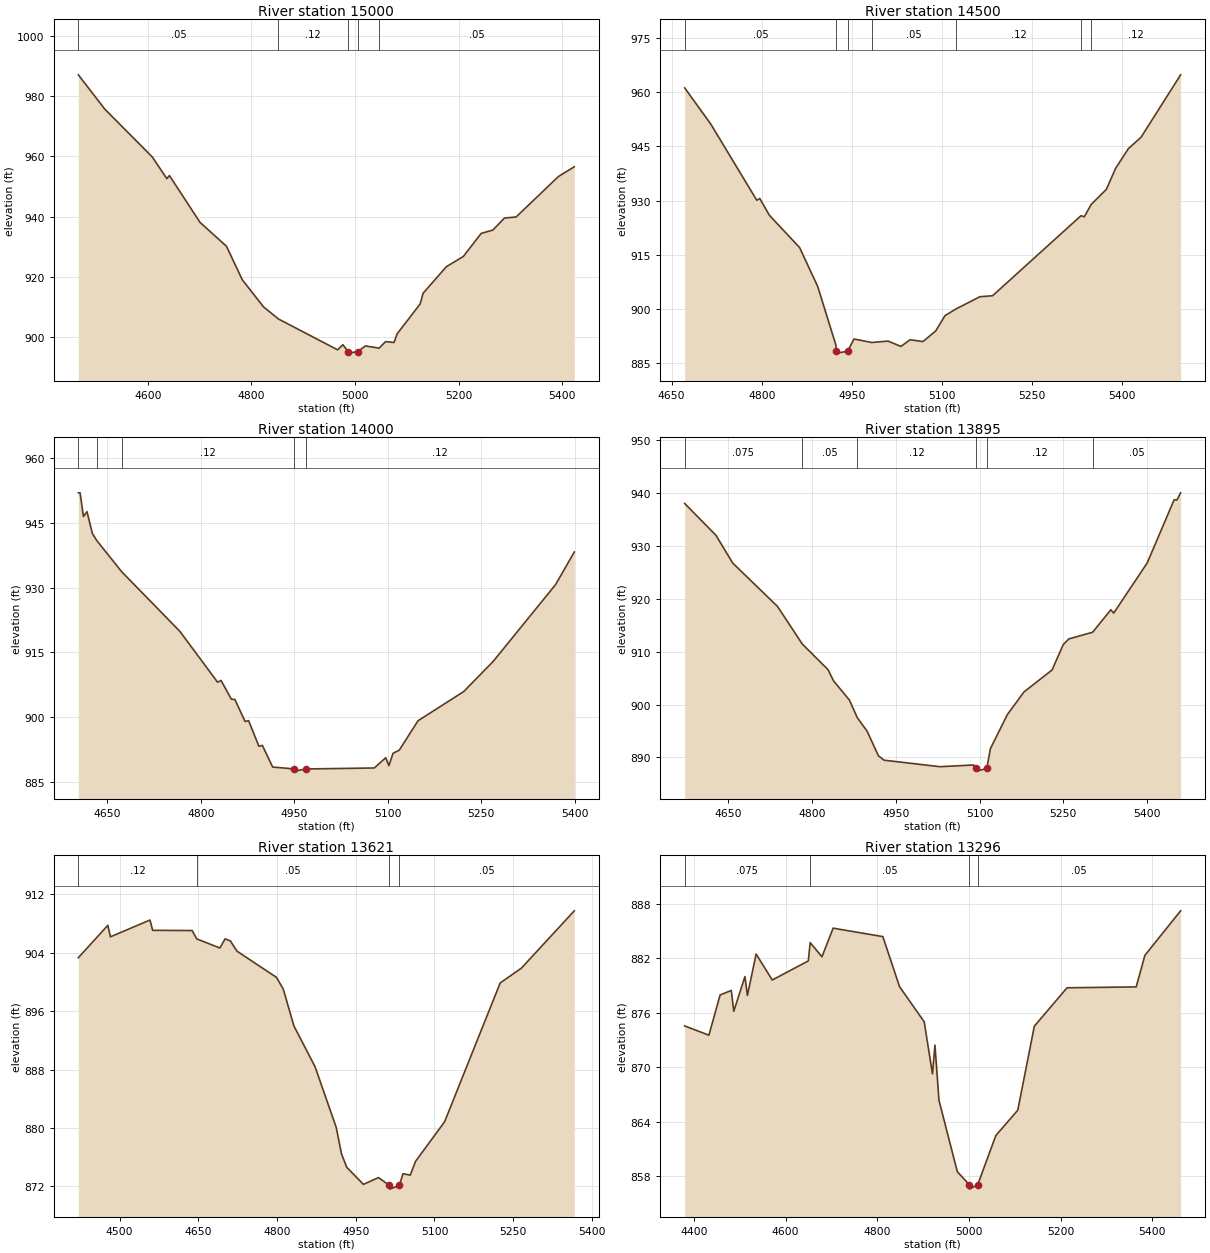
Type RM Length L Ch R = 1,15000,500,500,500
BEGIN DESCRIPTION:
SLICKROCK CREEK 30.0
END DESCRIPTION:
XS GIS Cut Line= 3
      2915705.72     10163103.10      2916228.69     10162995.10
      2916605.71     10162803.10
#Sta/Elev= 30
  4466.0  987.02  4517.0  975.67  4608.9  959.77  4636.7  952.63  4641.8  953.65
  4700.8  938.14  4751.9  930.22  4782.4  919.12  4823.3  910.16  4852.2  906.13
  4966.3  895.92  4976.5  897.60  4986.7  895.32  4987.2  894.82  5005.2  895.32
  5020.0  897.21  5046.5  896.47  5058.9  898.64  5075.2  898.35  5081.2  901.20
  5125.6  911.10  5131.3  914.65  5176.2  923.45  5209.0  926.85  5243.5  934.49
  5266.0  935.59  5288.4  939.58  5310.8  939.92  5392.5  953.33  5423.1  956.56
#Mann=5,-1,0
  4466.0    0.05       0  4852.2    0.12       0  4986.7    0.07       0
  5005.2    0.12       0  5046.5    0.05       0
Bank Sta=4986.7,5005.2
Exp/Cntr=0.3,0.1

Type RM Length L Ch R = 1,14500,500,500,500
BEGIN DESCRIPTION:
SLICKROCK CREEK 29.0
END DESCRIPTION:
XS GIS Cut Line= 3
      2915855.71     10163453.11      2916181.61     10163492.71
      2916605.65     10163753.09
#Sta/Elev= 30
  4671.7  961.14  4715.1  951.17  4791.8  930.07  4796.8  930.57  4812.7  925.95
  4863.1  917.00  4893.3  906.22  4923.5  890.06  4924.2  888.31  4924.7  887.81
  4942.9  888.31  4953.7  891.71  4983.5  890.75  5010.5  891.14  5031.8  889.66
  5047.2  891.52  5068.5  891.00  5089.8  893.95  5105.2  898.18  5124.2  900.08
  5163.2  903.40  5184.5  903.68  5331.7  925.81  5337.2  925.51  5348.7  928.92
  5373.9  933.08  5389.4  938.91  5410.6  944.36  5431.9  947.53  5497.6  964.76
#Mann=7,-1,0
  4671.7    0.05       0  4924.2    0.03       0  4942.9    0.05       0
  4983.5    0.05       0  5124.2    0.12       0  5331.7    0.05       0
  5348.7    0.12       0
Bank Sta=4924.2,4942.9
Exp/Cntr=0.3,0.1

Type RM Length L Ch R = 1,14000,105,105,105
BEGIN DESCRIPTION:
SLICKROCK CREEK 28.0
END DESCRIPTION:
XS GIS Cut Line= 3
      2915755.67     10163803.11      2916107.56     10163986.47
      2916505.67     10163953.11
#Sta/Elev= 30
  4603.2  951.93  4606.0  951.93  4611.4  946.45  4617.1  947.57  4625.8  942.50
  4632.6  940.92  4673.1  933.62  4766.1  919.89  4826.8  908.09  4832.4  908.50
  4848.9  904.15  4854.5  904.11  4871.0  899.00  4876.6  899.20  4893.1  893.27
  4898.7  893.46  4915.2  888.46  4950.0  888.01  4950.5  887.51  4968.7  888.01
  5078.4  888.24  5096.8  890.62  5101.8  888.77  5108.5  891.64  5118.5  892.36
  5148.6  899.17  5221.9  905.92  5269.1  912.88  5369.4  930.67  5399.5  938.23
#Mann=5,-1,0
  4603.2   0.075       0  4632.6    0.05       0  4673.1    0.12       0
  4950.0    0.07       0  4968.7    0.12       0
Bank Sta=4950,4968.7
Exp/Cntr=0.3,0.1

Type RM Length L Ch R = 1,13895,274,274,274
BEGIN DESCRIPTION:
Mapping XS e2841ac8
END DESCRIPTION:
XS GIS Cut Line= 2
      2915659.81     10164052.46      2916545.22     10164128.85
#Sta/Elev= 30
  4571.6  938.02  4627.7  932.00  4657.8  926.74  4738.1  918.54  4782.2  911.46
  4828.4  906.61  4838.5  904.46  4866.8  900.85  4880.9  897.53  4898.7  894.93
  4918.8  890.31  4928.8  889.48  5029.2  888.25  5089.4  888.57  5094.2  887.91
  5094.7  887.41  5112.9  887.91  5119.5  891.66  5149.6  898.06  5179.7  902.39
  5229.9  906.53  5250.0  911.34  5260.0  912.41  5302.6  913.67  5335.3  917.92
  5340.4  917.29  5400.5  926.79  5448.7  938.72  5453.7  938.68  5460.3  940.03
#Mann=6,-1,0
  4571.6   0.075       0  4782.2    0.05       0  4880.9    0.12       0
  5094.2    0.07       0  5112.9    0.12       0  5302.6    0.05       0
Bank Sta=5094.2,5112.9
Exp/Cntr=0.3,0.1

Type RM Length L Ch R = 1,13621,325,325,325
BEGIN DESCRIPTION:
Mapping XS 58e9cacb
END DESCRIPTION:
XS GIS Cut Line= 2
      2915438.24     10164280.68      2916375.74     10164398.73
#Sta/Elev= 30
  4421.5  903.32  4477.7  907.76  4482.7  906.18  4558.0  908.48  4563.1  907.07
  4638.4  907.04  4647.0  905.90  4691.1  904.65  4701.1  905.90  4711.2  905.62
  4723.7  904.22  4799.0  900.63  4812.0  899.01  4832.2  893.98  4872.5  888.39
  4912.8  880.09  4922.9  876.45  4932.9  874.62  4964.7  872.28  4993.4  873.21
  5014.3  872.13  5014.8  871.63  5033.0  872.13  5040.0  873.74  5053.9  873.55
  5064.0  875.44  5119.4  880.86  5225.2  899.86  5265.6  901.89  5366.4  909.74
#Mann=4,-1,0
  4421.5    0.12       0  4647.0    0.05       0  5014.3    0.05       0
  5033.0    0.05       0
Bank Sta=5014.3,5033
Exp/Cntr=0.3,0.1

Type RM Length L Ch R = 1,13296,447,447,447
BEGIN DESCRIPTION:
Mapping XS 57a31b16
END DESCRIPTION:
XS GIS Cut Line= 2
      2915299.39     10164419.58      2916306.28     10164815.39
#Sta/Elev= 30
  4379.8  874.56  4432.7  873.54  4457.1  877.97  4481.5  878.47  4486.9  876.17
  4511.3  880.00  4516.7  877.92  4535.7  882.48  4570.9  879.62  4649.5  881.72
  4653.6  883.74  4679.3  882.18  4703.7  885.33  4812.1  884.40  4848.6  878.88
  4902.3  875.02  4920.4  869.28  4925.8  872.44  4934.6  866.36  4974.6  858.50
  5000.5  857.08  5001.0  856.58  5019.2  857.08  5058.6  862.48  5106.5  865.28
  5142.6  874.53  5213.9  878.76  5364.8  878.86  5383.8  882.34  5461.7  887.24
#Mann=4,-1,0
  4379.8   0.075       0  4653.6    0.05       0  5000.5    0.05       0
  5019.2    0.05       0
Bank Sta=5000.5,5019.2
Exp/Cntr=0.3,0.1

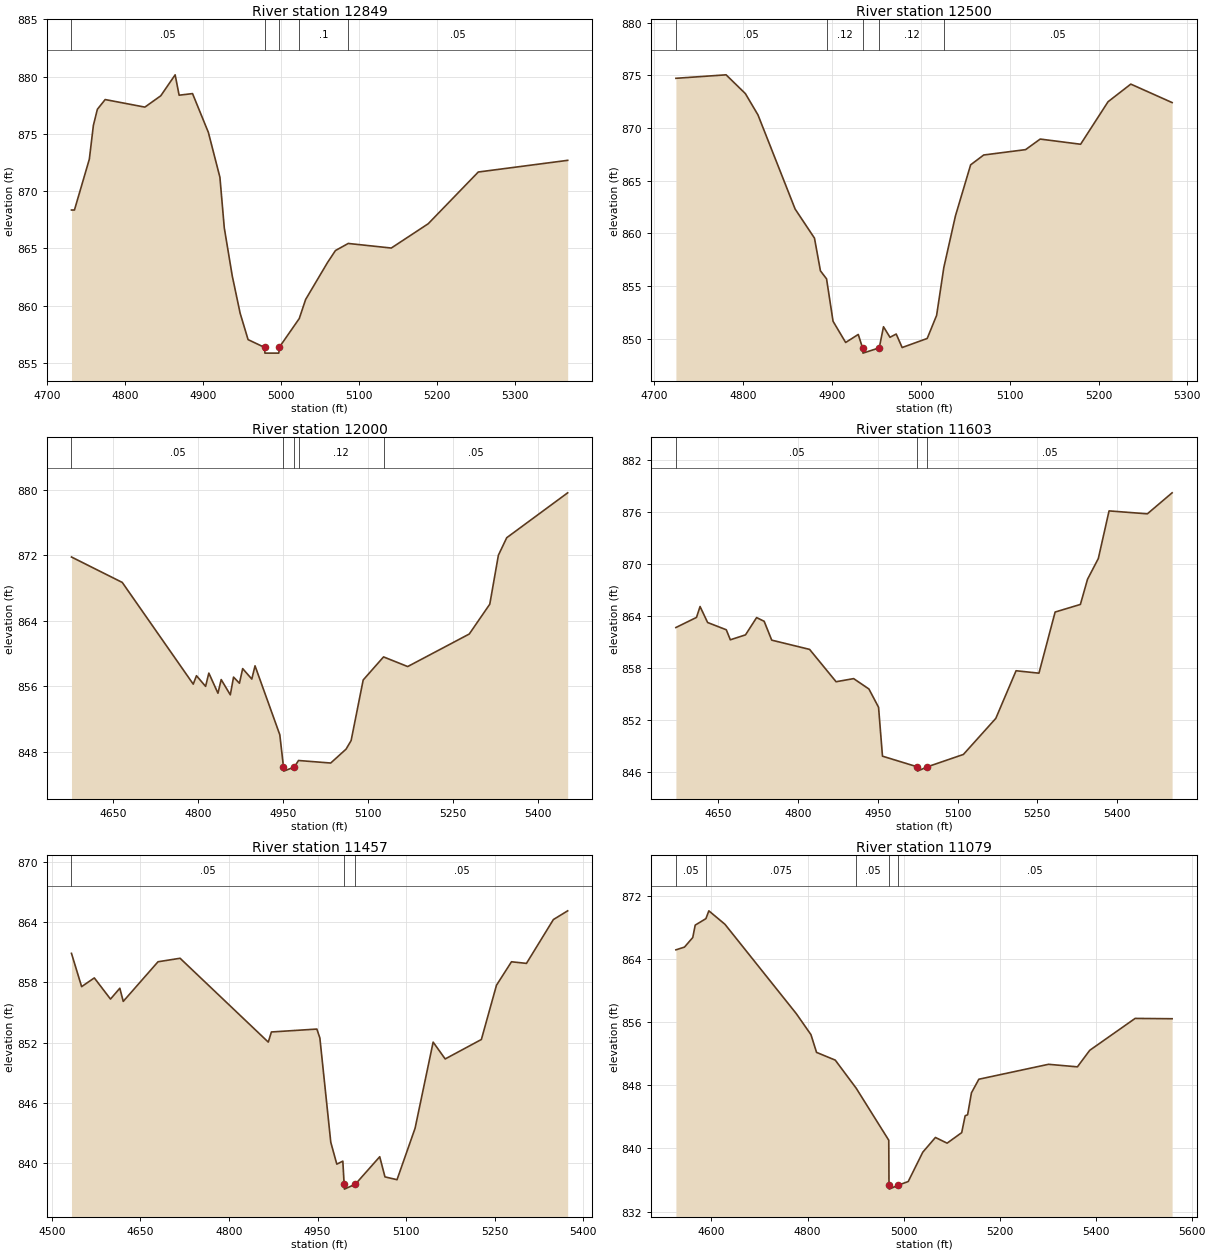
Type RM Length L Ch R = 1,12849,349,349,349
BEGIN DESCRIPTION:
Mapping XS 6cc9fa9a
END DESCRIPTION:
XS GIS Cut Line= 2
      2915463.20     10165012.87      2916088.25     10165130.93
#Sta/Elev= 30
  4731.4  868.35  4735.2  868.35  4754.3  872.79  4759.5  875.75  4764.6  877.15
  4774.6  878.00  4825.5  877.34  4845.9  878.33  4864.3  880.16  4869.4  878.38
  4886.6  878.52  4906.9  875.13  4921.7  871.21  4927.3  866.79  4937.5  862.60
  4947.6  859.34  4957.8  857.03  4978.9  856.35  4979.4  855.85  4997.2  855.85
  4997.7  856.35  5023.4  858.87  5031.6  860.54  5059.6  863.76  5069.8  864.81
  5086.2  865.43  5141.4  865.03  5188.7  867.15  5252.9  871.67  5367.5  872.69
#Mann=5,-1,0
  4731.4    0.05       0  4978.9    0.03       0  4997.7    0.05       0
  5023.4     0.1       0  5086.2    0.05       0
Bank Sta=4978.9,4997.7
Exp/Cntr=0.3,0.1

Type RM Length L Ch R = 1,12500,500,500,500
BEGIN DESCRIPTION:
SLICKROCK CREEK 25.0
END DESCRIPTION:
XS GIS Cut Line= 3
      2915505.66     10165203.08      2915688.98     10165409.14
      2915955.71     10165503.12
#Sta/Elev= 30
  4724.2  874.71  4780.7  875.04  4802.4  873.26  4816.6  871.24  4858.4  862.32
  4880.2  859.56  4886.9  856.46  4893.8  855.70  4901.1  851.68  4915.3  849.67
  4929.5  850.43  4934.3  849.16  4934.8  848.66  4953.1  849.16  4957.9  851.16
  4965.2  850.16  4972.2  850.47  4978.9  849.19  5007.1  850.05  5017.7  852.24
  5025.8  856.77  5038.9  861.67  5056.0  866.51  5070.7  867.44  5117.9  867.95
  5134.3  868.95  5179.8  868.46  5210.7  872.49  5236.3  874.16  5282.8  872.41
#Mann=5,-1,0
  4724.2    0.05       0  4893.8    0.12       0  4934.3    0.07       0
  4953.1    0.12       0  5025.8    0.05       0
Bank Sta=4934.3,4953.1
Exp/Cntr=0.3,0.1

Type RM Length L Ch R = 1,12000,397,397,397
BEGIN DESCRIPTION:
SLICKROCK CREEK 24.0
END DESCRIPTION:
XS GIS Cut Line= 3
      2915105.70     10165653.12      2915477.00     10165856.39
      2915855.71     10166103.13
#Sta/Elev= 30
  4576.7  871.80  4666.3  868.69  4791.5  856.25  4797.2  857.28  4813.3  855.98
  4819.0  857.60  4835.1  855.14  4840.8  856.81  4856.9  854.94  4862.6  857.11
  4873.0  856.36  4878.7  858.15  4894.8  856.87  4900.5  858.49  4944.2  850.06
  4950.7  846.11  4951.2  845.61  4969.8  846.11  4977.2  846.91  5034.0  846.60
  5061.1  848.30  5070.0  849.35  5091.3  856.76  5127.2  859.58  5169.8  858.40
  5278.4  862.38  5314.6  866.03  5329.8  872.02  5344.5  874.16  5452.0  879.65
#Mann=5,-1,0
  4576.7    0.05       0  4950.7    0.07       0  4969.8    0.05       0
  4977.2    0.12       0  5127.2    0.05       0
Bank Sta=4950.7,4969.8
Exp/Cntr=0.3,0.1

Type RM Length L Ch R = 1,11603,146,146,146
BEGIN DESCRIPTION:
Mapping XS 587ab28f
END DESCRIPTION:
XS GIS Cut Line= 4
      2915060.80     10165983.91      2915243.54     10166191.68
      2915336.14     10166234.23      2915882.49     10166326.54
#Sta/Elev= 30
  4570.6  862.67  4609.3  863.84  4616.0  865.10  4630.2  863.25  4665.3  862.41
  4672.9  861.25  4701.4  861.82  4722.3  863.82  4736.5  863.39  4750.7  861.21
  4821.9  860.14  4871.7  856.40  4904.7  856.76  4933.4  855.56  4951.5  853.45
  4958.9  847.79  5024.1  846.56  5024.6  846.06  5043.3  846.56  5111.0  847.99
  5171.9  852.16  5210.0  857.67  5253.0  857.39  5283.4  864.46  5330.9  865.34
  5344.3  868.25  5364.6  870.65  5384.8  876.16  5456.8  875.82  5503.3  878.25
#Mann=3,-1,0
  4570.6    0.05       0  5024.1    0.03       0  5043.3    0.05       0
Bank Sta=5024.1,5043.3
Exp/Cntr=0.3,0.1

Type RM Length L Ch R = 1,11457,378,378,378
BEGIN DESCRIPTION:
Mapping XS 6cc95d9c
END DESCRIPTION:
XS GIS Cut Line= 5
      2914900.63     10166296.79      2915070.84     10166394.42
      2915138.42     10166401.92      2915253.55     10166361.88
      2915699.02     10166451.97
#Sta/Elev= 30
  4533.2  860.90  4550.4  857.58  4571.9  858.45  4599.3  856.34  4615.1  857.42
  4620.9  856.11  4679.8  860.06  4717.2  860.41  4866.6  852.05  4871.9  853.06
  4948.9  853.35  4954.0  852.46  4972.5  842.06  4982.7  839.88  4992.9  840.18
  4995.1  837.89  4995.6  837.39  5014.3  837.89  5055.4  840.62  5064.3  838.61
  5084.7  838.33  5115.3  843.46  5145.9  852.05  5166.3  850.37  5227.6  852.31
  5253.2  857.72  5278.6  860.06  5304.0  859.90  5349.6  864.27  5373.8  865.14
#Mann=3,-1,0
  4533.2    0.05       0  4995.1    0.03       0  5014.3    0.05       0
Bank Sta=4995.1,5014.3
Exp/Cntr=0.3,0.1

Type RM Length L Ch R = 1,11079,497,497,497
BEGIN DESCRIPTION:
Mapping XS 7d1cd359
END DESCRIPTION:
XS GIS Cut Line= 3
      2914788.00     10166672.23      2915411.23     10166772.35
      2915812.48     10166799.76
#Sta/Elev= 30
  4525.9  865.13  4543.8  865.48  4561.0  866.69  4566.1  868.26  4588.4  869.08
  4594.5  870.07  4628.0  868.37  4776.8  857.04  4807.1  854.40  4818.8  852.15
  4857.8  851.17  4901.3  847.62  4969.2  841.03  4969.7  835.34  4970.2  834.84
  4988.9  835.34  5009.7  835.80  5040.1  839.52  5066.4  841.38  5090.7  840.66
  5121.1  841.99  5128.3  844.13  5133.4  844.25  5141.4  847.03  5156.8  848.75
  5301.9  850.64  5362.1  850.32  5387.7  852.41  5482.3  856.45  5559.3  856.41
#Mann=5,-1,0
  4525.9    0.05       0  4588.4   0.075       0  4901.3    0.05       0
  4969.7    0.03       0  4988.9    0.05       0
Bank Sta=4969.7,4988.9
Exp/Cntr=0.3,0.1

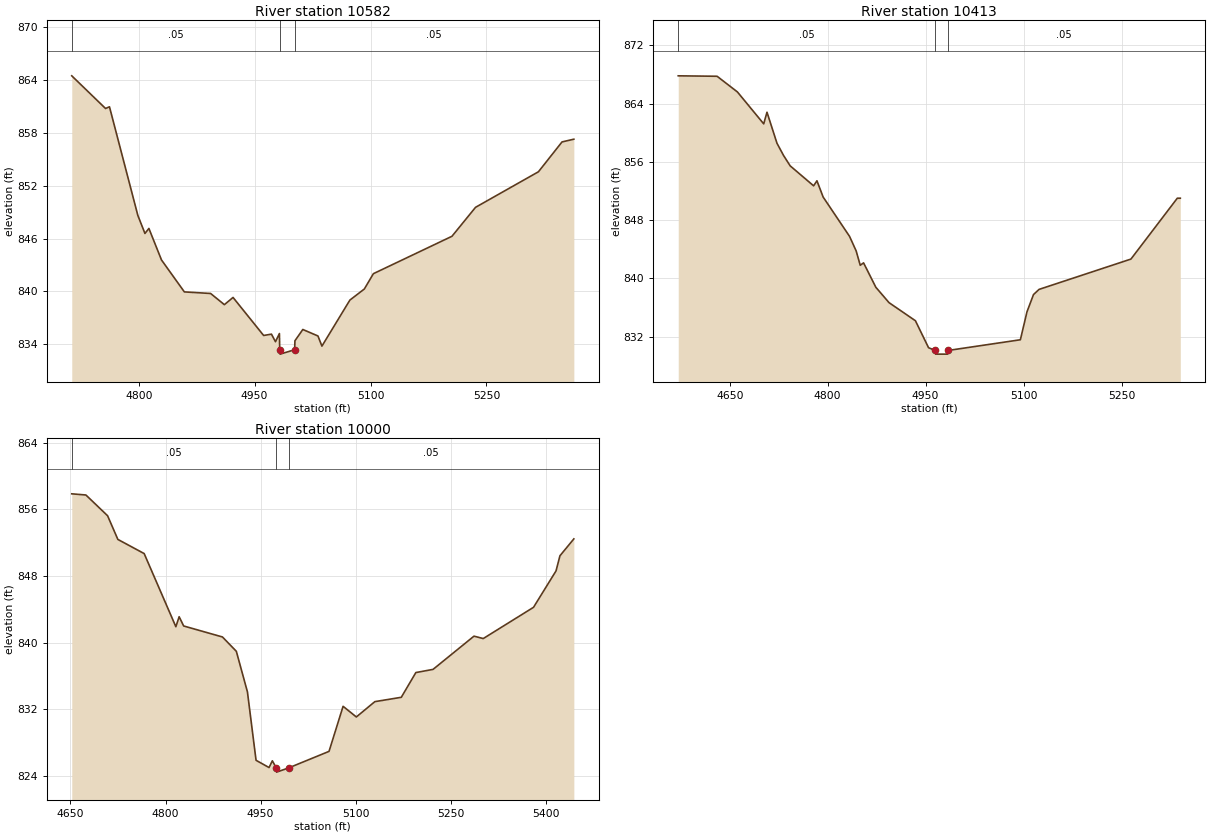
Type RM Length L Ch R = 1,10582,169,169,169
BEGIN DESCRIPTION:
Mapping XS 5039f4c0
END DESCRIPTION:
XS GIS Cut Line= 4
      2915111.88     10167148.74      2915285.45     10167183.45
      2915528.51     10167225.12      2915750.73     10167183.45
#Sta/Elev= 30
  4713.4  864.49  4757.1  860.78  4762.2  860.97  4798.9  848.63  4808.1  846.58
  4813.2  847.15  4829.5  843.57  4859.1  839.94  4893.1  839.76  4910.9  838.49
  4922.1  839.31  4961.7  834.99  4971.8  835.14  4977.0  834.28  4982.1  835.21
  4982.5  833.37  4983.0  832.87  5001.8  833.37  5002.2  834.39  5012.4  835.67
  5032.0  834.93  5037.1  833.78  5073.3  839.01  5092.0  840.27  5103.7  842.01
  5205.4  846.26  5235.9  849.55  5317.3  853.59  5347.8  856.98  5363.1  857.29
#Mann=3,-1,0
  4713.4    0.05       0  4982.5    0.05       0  5001.8    0.05       0
Bank Sta=4982.5,5001.8
Exp/Cntr=0.3,0.1

Type RM Length L Ch R = 1,10413,413,413,413
BEGIN DESCRIPTION:
Mapping XS f5d658af
END DESCRIPTION:
XS GIS Cut Line= 4
      2914965.96     10167329.28      2915313.23     10167377.90
      2915528.51     10167357.06      2915729.89     10167343.17
#Sta/Elev= 30
  4571.2  867.80  4630.7  867.74  4661.8  865.59  4702.1  861.21  4707.1  862.81
  4722.4  858.55  4732.5  856.87  4742.6  855.45  4778.5  852.71  4783.6  853.40
  4793.1  851.17  4833.5  845.78  4843.6  843.79  4849.9  841.81  4855.0  842.14
  4873.8  838.79  4894.0  836.68  4934.4  834.20  4954.5  830.50  4964.9  830.12
  4965.4  829.62  4983.7  829.62  4984.2  830.12  5095.1  831.59  5105.2  835.42
  5115.2  837.79  5123.7  838.50  5264.4  842.66  5335.4  851.01  5340.0  851.01
#Mann=3,-1,0
  4571.2    0.05       0  4964.9    0.03       0  4984.2    0.05       0
Bank Sta=4964.9,4984.2
Exp/Cntr=0.3,0.1

Type RM Length L Ch R = 1,10000,500,500,500
BEGIN DESCRIPTION:
SLICKROCK CREEK 20.0
END DESCRIPTION:
XS GIS Cut Line= 3
      2915155.68     10167853.11      2915490.77     10167759.59
      2915755.66     10167403.14
#Sta/Elev= 30
  4652.1  857.87  4674.4  857.73  4708.6  855.24  4724.8  852.40  4766.3  850.70
  4816.3  841.92  4821.5  843.12  4828.6  842.01  4889.8  840.69  4911.7  838.97
  4929.2  834.10  4942.8  825.89  4963.3  825.02  4968.5  825.83  4974.7  824.97
  4975.2  824.47  4994.0  824.97  5057.9  826.96  5080.1  832.37  5101.0  831.09
  5130.2  832.93  5171.9  833.45  5194.9  836.42  5222.0  836.80  5286.6  840.79
  5301.2  840.50  5380.5  844.25  5416.0  848.62  5422.2  850.44  5444.1  852.46
#Mann=3,-1,0
  4652.1    0.05       0  4974.7    0.03       0  4994.0    0.05       0
Bank Sta=4974.7,4994
Exp/Cntr=0.3,0.1