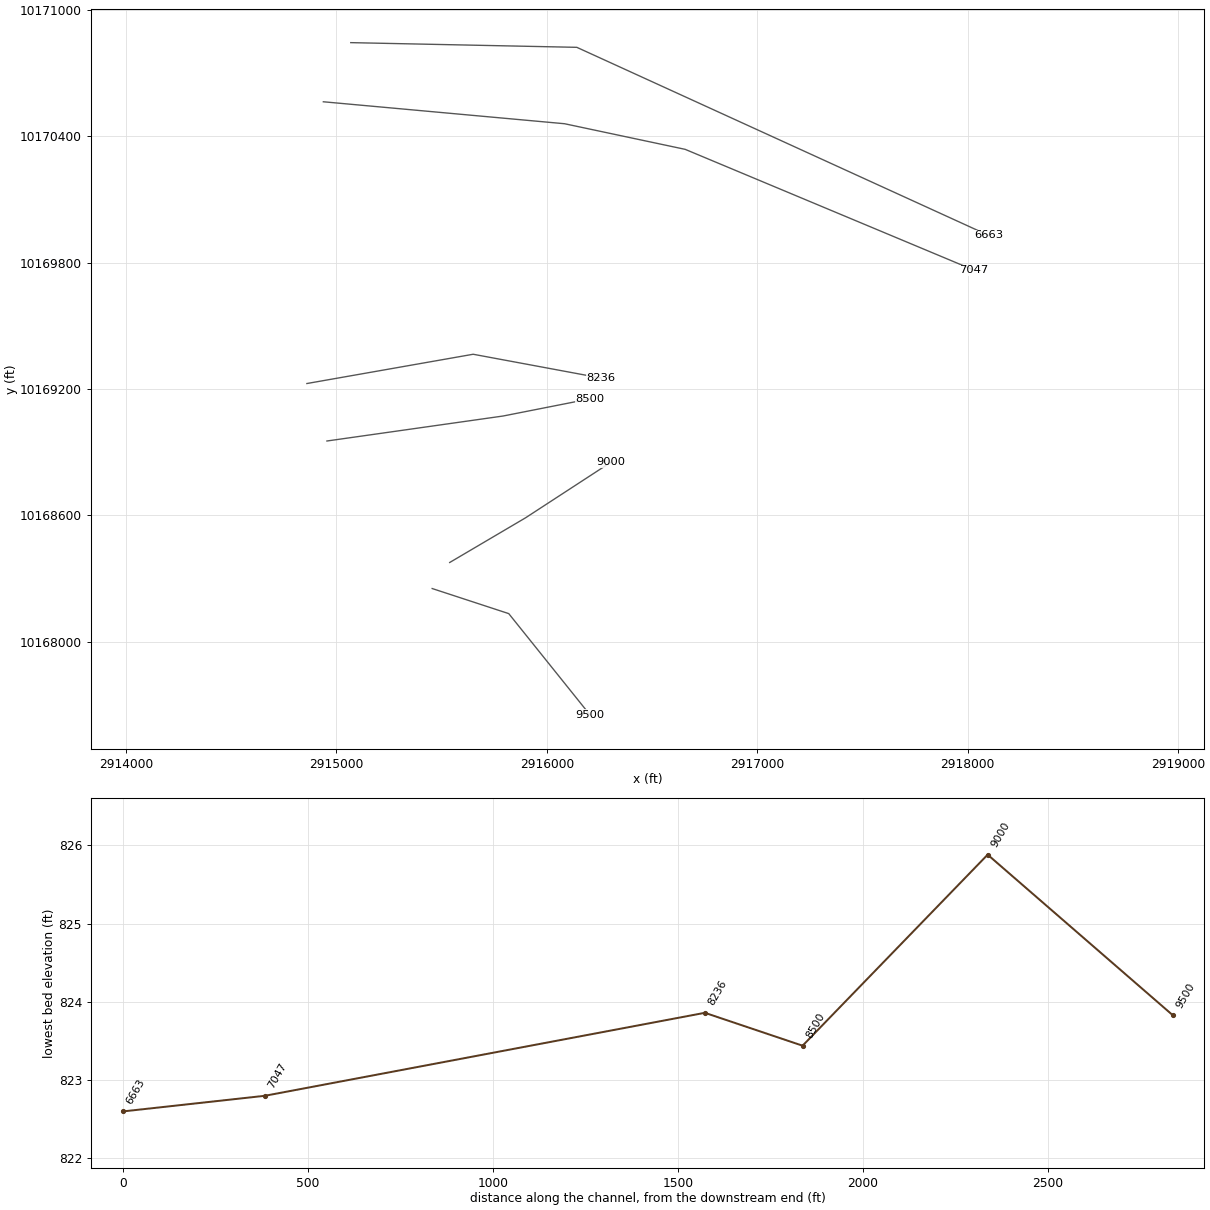
HEC-RAS study SLICKROCK CREEK.prj: SLICKROCK CREEK Base Level Engineering

--- SLICKROCK CREEK.g01 (geometry) --- (continued)

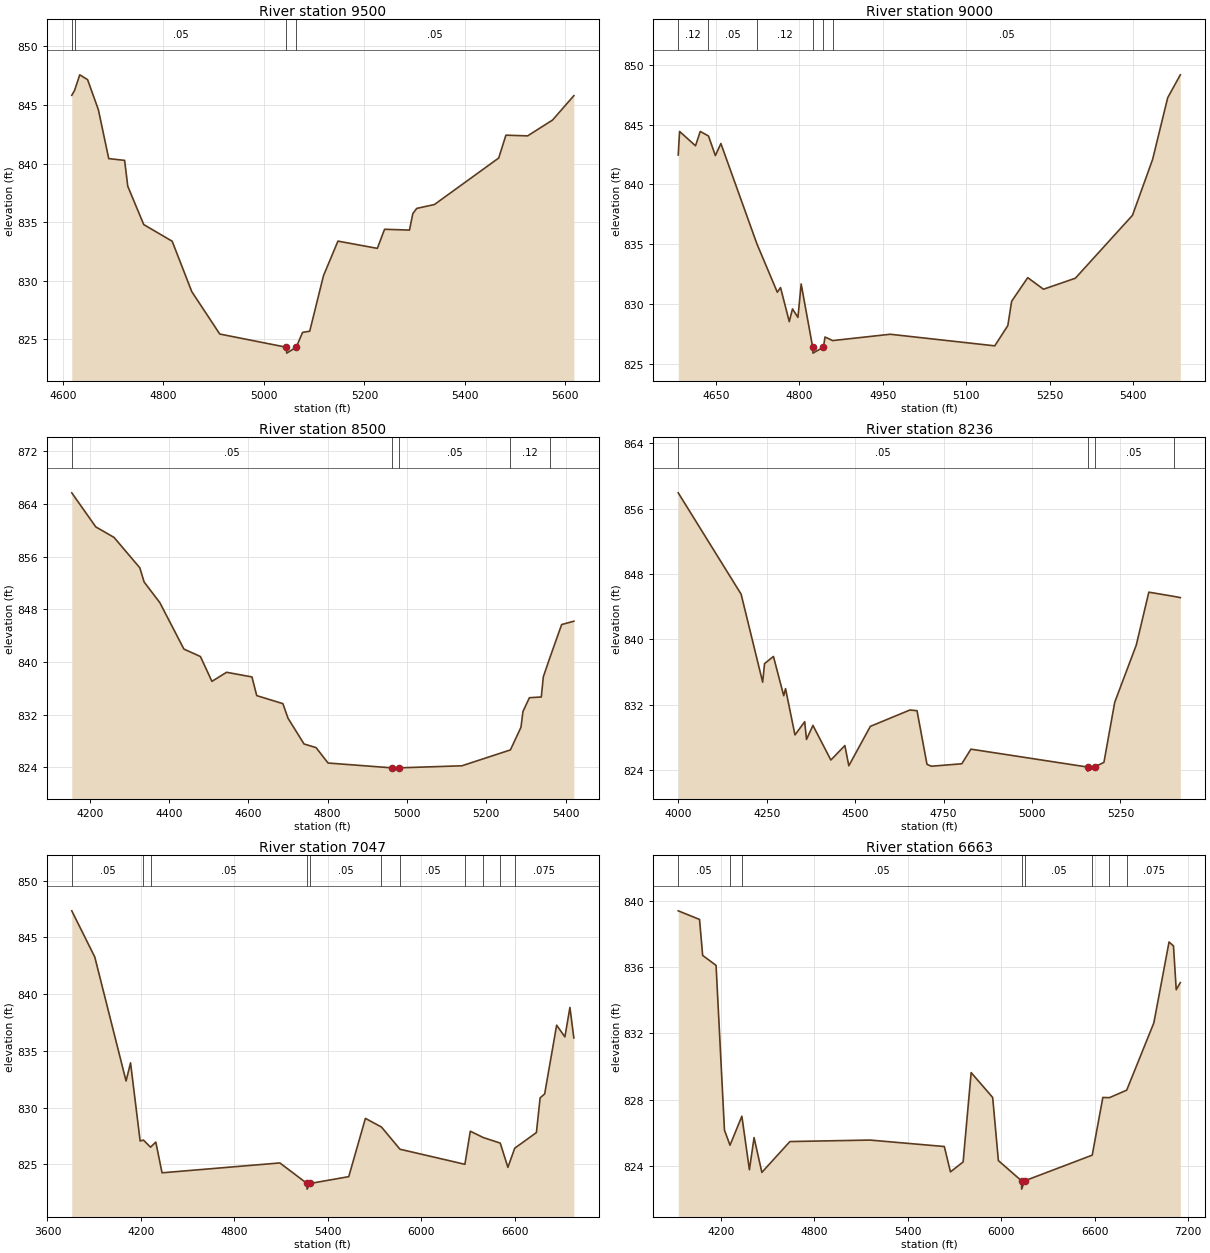
Type RM Length L Ch R = 1,9500,500,500,500
BEGIN DESCRIPTION:
SLICKROCK CREEK 19.0
END DESCRIPTION:
XS GIS Cut Line= 3
      2915455.72     10168253.10      2915819.35     10168134.10
      2916205.66     10167653.14
#Sta/Elev= 30
  4617.4  845.83  4622.9  846.24  4633.3  847.58  4648.9  847.17  4670.4  844.60
  4691.0  840.43  4722.6  840.28  4728.9  838.07  4760.7  834.80  4817.3  833.38
  4856.3  829.08  4912.0  825.46  5044.8  824.33  5045.3  823.83  5064.2  824.33
  5076.9  825.60  5091.1  825.70  5118.5  830.44  5147.3  833.39  5225.7  832.77
  5240.1  834.40  5289.7  834.33  5296.3  835.73  5304.1  836.18  5339.3  836.51
  5467.3  840.48  5481.7  842.43  5524.9  842.37  5574.5  843.72  5616.9  845.80
#Mann=4,-1,0
  4617.4    0.12       0  4622.9    0.05       0  5044.8    0.05       0
  5064.2    0.05       0
Bank Sta=5044.8,5064.2
Exp/Cntr=0.3,0.1

Type RM Length L Ch R = 1,9000,500,500,500
BEGIN DESCRIPTION:
SLICKROCK CREEK 18.0
END DESCRIPTION:
XS GIS Cut Line= 3
      2915538.89     10168376.69      2915899.06     10168588.62
      2916305.71     10168853.13
#Sta/Elev= 30
  4582.1  842.47  4584.5  844.44  4613.2  843.24  4621.7  844.44  4636.5  844.06
  4648.9  842.42  4658.8  843.43  4723.6  835.03  4760.3  830.98  4766.1  831.37
  4781.8  828.52  4787.6  829.58  4797.4  828.87  4803.2  831.67  4823.9  826.38
  4824.4  825.88  4843.3  826.38  4846.1  827.23  4859.9  826.93  4963.3  827.46
  5151.4  826.49  5174.9  828.19  5181.7  830.22  5210.7  832.20  5239.0  831.23
  5296.3  832.15  5399.1  837.42  5435.3  842.10  5462.4  847.26  5485.1  849.18
#Mann=6,-1,0
  4582.1    0.12       0  4636.5    0.05       0  4723.6    0.12       0
  4823.9    0.03       0  4843.3    0.12       0  4859.9    0.05       0
Bank Sta=4823.9,4843.3
Exp/Cntr=0.3,0.1

Type RM Length L Ch R = 1,8500,264,264,264
BEGIN DESCRIPTION:
SLICKROCK CREEK 17.0
END DESCRIPTION:
XS GIS Cut Line= 3
      2914955.71     10168953.11      2915792.75     10169071.69
      2916205.70     10169153.11
#Sta/Elev= 30
  4154.6  865.67  4215.2  860.50  4261.1  858.91  4326.3  854.29  4337.1  852.14
  4376.8  849.00  4437.4  841.96  4479.1  840.83  4508.1  837.06  4545.1  838.44
  4609.1  837.73  4621.1  834.90  4687.1  833.68  4700.0  831.47  4740.4  827.56
  4770.7  827.01  4801.0  824.67  4961.3  823.94  4961.8  823.44  4980.9  823.94
  5138.6  824.25  5260.9  826.66  5287.5  830.09  5292.6  832.49  5308.8  834.58
  5338.8  834.69  5343.9  837.75  5360.6  840.68  5390.1  845.68  5420.9  846.19
#Mann=5,-1,0
  4154.6    0.05       0  4961.3    0.03       0  4980.9    0.05       0
  5260.9    0.12       0  5360.6    0.05       0
Bank Sta=4961.3,4980.9
Exp/Cntr=0.3,0.1

Type RM Length L Ch R = 1,8236,1189,1189,1189
BEGIN DESCRIPTION:
Mapping XS a3a7b512
END DESCRIPTION:
XS GIS Cut Line= 3
      2914860.46     10169225.79      2915650.39     10169364.68
      2916258.06     10169251.83
#Sta/Elev= 30
  3999.3  857.93  4177.2  845.52  4238.1  834.75  4243.4  837.02  4268.6  837.90
  4297.7  833.09  4302.8  833.96  4329.5  828.29  4357.0  829.91  4362.1  827.74
  4380.3  829.46  4431.0  825.22  4470.6  826.99  4481.8  824.52  4542.7  829.34
  4654.4  831.34  4674.7  831.26  4702.9  824.69  4715.3  824.46  4801.3  824.76
  4827.1  826.55  5157.1  824.36  5157.6  823.86  5176.7  824.36  5203.4  824.94
  5233.9  832.29  5294.9  839.30  5330.4  845.77  5401.5  845.25  5419.4  845.10
#Mann=4,-1,0
  3999.3    0.05       0  5157.1    0.03       0  5176.7    0.05       0
  5401.5    0.12       0
Bank Sta=5157.1,5176.7
Exp/Cntr=0.3,0.1

Type RM Length L Ch R = 1,7047,384,384,384
BEGIN DESCRIPTION:
Mapping XS c9ab2223
END DESCRIPTION:
XS GIS Cut Line= 4
      2914938.60     10170562.60      2916084.42     10170458.43
      2916657.34     10170336.91      2918028.87     10169763.99
#Sta/Elev= 30
  3755.9  847.35  3903.6  843.28  4104.4  832.34  4133.2  833.94  4194.8  827.04
  4215.8  827.13  4261.5  826.50  4295.2  826.95  4335.4  824.24  5091.7  825.11
  5265.8  823.30  5266.3  822.80  5285.6  823.30  5533.7  823.90  5640.6  829.04
  5743.6  828.28  5862.5  826.32  6279.2  824.99  6313.9  827.91  6397.2  827.35
  6506.2  826.86  6555.2  824.72  6599.0  826.41  6738.2  827.79  6762.0  830.85
  6791.2  831.20  6868.1  837.26  6921.1  836.23  6953.4  838.83  6978.5  836.14
#Mann=11,-1,0
  3755.9    0.05       0  4215.8   0.075       0  4261.5    0.05       0
  5265.8    0.03       0  5285.6    0.05       0  5743.6   0.075       0
  5862.5    0.05       0  6279.2     0.1       0  6397.2   0.075       0
  6506.2     0.1       0  6599.0   0.075       0
Bank Sta=5265.8,5285.6
Exp/Cntr=0.3,0.1

Type RM Length L Ch R = 1,6663,0,0,0
BEGIN DESCRIPTION:
SLICKROCK CREEK 16.0
END DESCRIPTION:
XS GIS Cut Line= 3
      2915068.92     10170843.17      2916142.79     10170820.90
      2918098.27     10169928.94
#Sta/Elev= 30
  3925.9  839.39  4062.7  838.87  4082.7  836.70  4168.8  836.10  4222.7  826.16
  4258.3  825.25  4334.5  827.00  4382.8  823.77  4412.8  825.71  4462.8  823.61
  4642.8  825.47  5157.1  825.56  5634.2  825.17  5673.6  823.64  5754.9  824.24
  5806.5  829.63  5944.7  828.13  5981.4  824.32  6130.1  823.10  6130.6  822.60
  6149.9  823.10  6583.8  824.65  6651.9  828.13  6694.5  828.12  6805.1  828.57
  6979.4  832.63  7077.0  837.51  7105.5  837.27  7123.1  834.63  7149.3  835.06
#Mann=8,-1,0
  3925.9    0.05       0  4258.3   0.075       0  4334.5    0.05       0
  6130.1    0.03       0  6149.9    0.05       0  6583.8   0.075       0
  6694.5     0.1       0  6805.1   0.075       0
Bank Sta=6130.1,6149.9
Exp/Cntr=0.3,0.1

Chan Stop Cuts=-1