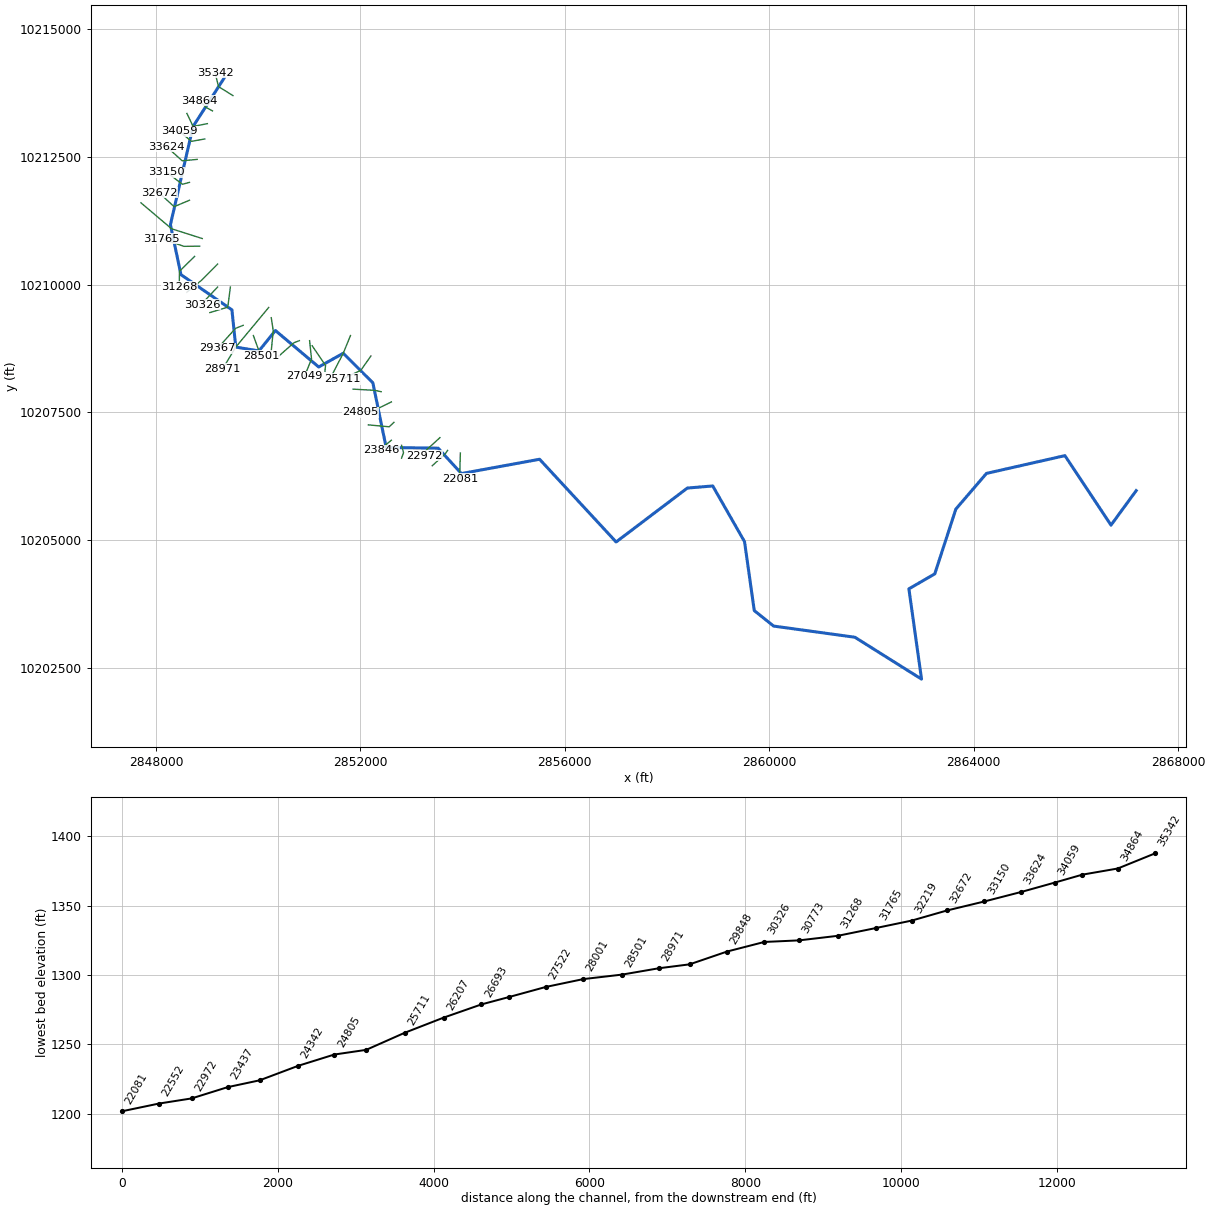
--- BEDFORD CREEK.prj (project) ---

Proj Title=BEDFORD CREEK Base Level Engineering
Current Plan=p01
Default Exp/Contr=0.3,0.1
English Units
Geom File=g01
Flow File=f01
Plan File=p01
Y Axis Title=Elevation
X Axis Title(PF)=Main Channel Distance
X Axis Title(XS)=Station
BEGIN DESCRIPTION:
BEDFORD CREEK
END DESCRIPTION:
DSS Export Rating Curves= 0
DSS Export Rating Curve Sorted= 0
DSS Export Volume Flow Curves= 0
DXF OffsetX= 0
DXF OffsetY= 0
DXF ScaleX= 1
DXF ScaleY= 10

--- BEDFORD CREEK.p01 (plan) ---

Plan Title=Multiple Run
Short Identifier=Multiple
Geom File=g01
Flow File=f01
Subcritical Flow
K Sum by GR= 0
Std Step Tol= 0.01
Critical Tol= 0.01
Num of Std Step Trials= 20
Max Error Tol= 0.3
Flow Tol Ratio= 0.001
Split Flow NTrial= 30
Split Flow Tol= 0.02
Split Flow Ratio= 0.02
Log Output Level= 0
Friction Slope Method= 1
Unsteady Friction Slope Method= 2
Unsteady Bridges Friction Slope Method= 1
Parabolic Critical Depth
Global Vel Dist=  1 , 1 , 1
Global Log Level= 0
CheckData=True
Encroach Param= -1, 0, 0, 0
BEGIN DESCRIPTION:
Multiple Run
END DESCRIPTION:

--- BEDFORD CREEK.f01 (steady flow) ---

Flow Title=Multiple
Number of Profiles=7
Profile Names=10-year,25-year,50-year,1pct_min,100-year,1pct_plu,500-year
River Rch & RM= BEDFORD CREEK,Reach-1,35342
     391     623     914     737    1220    2021    1679
River Rch & RM= BEDFORD CREEK,Reach-1,30773
     684    1141    1802    1327    2483    4648    3469
River Rch & RM= BEDFORD CREEK,Reach-1,23846
     924    1573    2917    2148    4136    7963    5879
River Rch & RM= BEDFORD CREEK,Reach-1,19838
    1223    2130    3900    2749    5583   11340    7946
River Rch & RM= BEDFORD CREEK,Reach-1,12610
    1536    2719    5154    3569    7468   15624   10672
River Rch & RM= BEDFORD CREEK,Reach-1,5841
    1578    2799    5292    3653    7673   16117   10961
River Rch & RM= BEDFORD CREEK,Reach-1,4859
    2151    3878    7903    5509   11626   24537   16594
Boundary for River Rch & Prof#=BEDFORD CREEK,Reach-1,1
Up Type=0
Dn Type=3
Dn Slope=0.005
Boundary for River Rch & Prof#=BEDFORD CREEK,Reach-1,2
Up Type=0
Dn Type=3
Dn Slope=0.005
Boundary for River Rch & Prof#=BEDFORD CREEK,Reach-1,3
Up Type=0
Dn Type=3
Dn Slope=0.005
Boundary for River Rch & Prof#=BEDFORD CREEK,Reach-1,4
Up Type=0
Dn Type=3
Dn Slope=0.005
Boundary for River Rch & Prof#=BEDFORD CREEK,Reach-1,5
Up Type=0
Dn Type=3
Dn Slope=0.005
Boundary for River Rch & Prof#=BEDFORD CREEK,Reach-1,6
Up Type=0
Dn Type=3
Dn Slope=0.005
Boundary for River Rch & Prof#=BEDFORD CREEK,Reach-1,7
Up Type=0
Dn Type=3
Dn Slope=0.005

--- BEDFORD CREEK.g01 (geometry) ---

Geom Title=Existing Conditions
Program Version=4.10

River Reach=BEDFORD CREEK   ,Reach-1
Reach XY= 30
       2849335.5       10214049.       2848726.5       10213099.
      2848282.75       10211176.       2848488.5       10210196.
        2849486.       10209506.       2849561.5       10208777.
      2850014.75       10208702.      2850336.75       10209101.
      2851184.25       10208387.      2851664.25       10208656.
      2852243.75       10208077.        2852504.       10206811.
       2853520.5       10206797.      2853976.75       10206300.
      2855505.75       10206580.      2857003.25       10204960.
        2858397.       10206016.      2858893.75       10206057.
      2859515.75       10204966.      2859706.25       10203616.
       2860084.5       10203313.        2861675.       10203094.
      2862978.75       10202274.      2862731.75       10204042.
        2863238.       10204335.       2863650.5       10205604.
       2864249.5       10206303.       2865784.5       10206651.
        2866686.       10205290.      2867179.25       10205966.

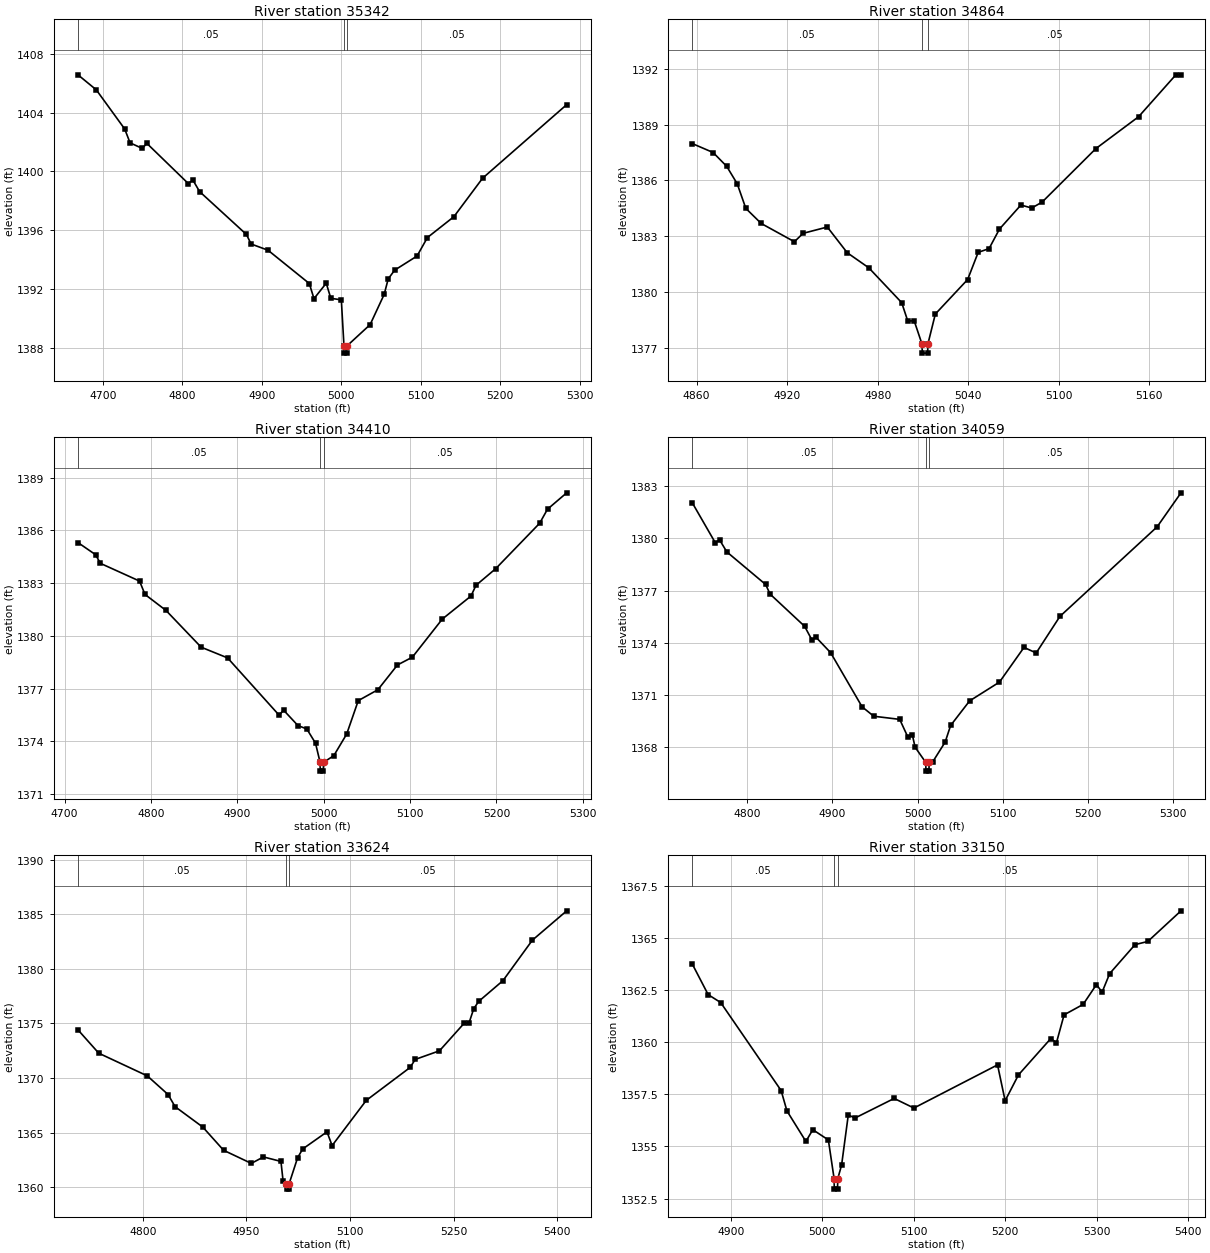
Type RM Length L Ch R = 1 ,35342   ,478,478,478
BEGIN DESCRIPTION:
BEDFORD CREEK 76.0
END DESCRIPTION:
XS GIS Cut Line= 3
      2849505.64     10213703.14      2849224.25       10213878.
      2849155.69     10214153.09
#Sta/Elev= 30
  4668.7 1406.57  4691.7 1405.55  4727.5 1402.88  4734.2 1401.94  4749.5 1401.56
  4755.4  1401.9  4807.4 1399.17  4813.3  1399.4  4821.7 1398.62  4880.6  1395.7
  4886.5 1395.05  4907.7 1394.63  4959.7 1392.36  4965.6 1391.33    4981 1392.38
  4986.8 1391.35    5000 1391.25  5003.3 1388.12  5003.5 1387.62    5007 1387.62
  5007.3 1388.12  5036.2 1389.56  5053.9 1391.62    5059 1392.68  5067.1 1393.27
  5095.2 1394.23  5108.3 1395.49  5141.6 1396.91  5177.7 1399.53  5283.5 1404.54
#Mann= 3 ,-1 , 0
  4668.7     .05       0  5003.3     .03       0  5007.3     .05       0
Bank Sta=5003.3,5007.3
XS Rating Curve= 0 ,0
Exp/Cntr=0.3,0.1

Type RM Length L Ch R = 1 ,34864   ,454,454,454
BEGIN DESCRIPTION:
BEDFORD CREEK 75.0
END DESCRIPTION:
XS GIS Cut Line= 3
       2849105.7     10213403.11       2848980.5       10213472.
       2848855.7      10213603.1
#Sta/Elev= 30
  4857.1 1387.98  4870.9  1387.5  4879.9 1386.76  4886.9 1385.82  4892.6  1384.5
  4902.8 1383.69  4924.8 1382.71  4930.5 1383.16  4946.6  1383.5  4959.8 1382.12
  4974.1 1381.31  4995.9 1379.44  4999.9 1378.46  5004.2 1378.46  5009.3 1377.23
  5009.6 1376.73  5013.1 1376.73  5013.3 1377.23  5018.2 1378.83  5039.6 1380.68
  5046.6 1382.14  5053.8 1382.34  5060.7 1383.39  5074.9 1384.68  5082.1 1384.52
    5089 1384.84  5124.6 1387.71  5152.9 1389.42  5177.6 1391.67    5181 1391.67
#Mann= 3 ,-1 , 0
  4857.1     .05       0  5009.3     .03       0  5013.3     .05       0
Bank Sta=5009.3,5013.3
XS Rating Curve= 0 ,0
Exp/Cntr=0.3,0.1

Type RM Length L Ch R = 1 ,34410   ,351,351,351
BEGIN DESCRIPTION:
BEDFORD CREEK 74.0
END DESCRIPTION:
XS GIS Cut Line= 3
       2849005.7     10213153.12       2848726.5       10213099.
      2848605.67     10213353.14
#Sta/Elev= 30
  4715.6 1385.31    4736 1384.62  4741.5 1384.13  4786.9 1383.12  4793.2 1382.36
  4817.5 1381.45  4858.2 1379.36  4888.8 1378.75  4948.5 1375.49  4953.6 1375.78
  4970.3  1374.9  4980.5 1374.71  4990.6  1373.9  4995.9 1372.81  4996.1 1372.31
  4999.6 1372.31  4999.9 1372.81  5011.8 1373.19  5026.7 1374.42  5040.1 1376.32
  5062.8 1376.94  5085.5 1378.35  5102.7 1378.79  5137.4 1380.96  5170.6 1382.27
  5176.4 1382.88  5199.1 1383.82  5250.1 1386.41  5259.2 1387.21  5281.4 1388.14
#Mann= 3 ,-1 , 0
  4715.6     .05       0  4995.9     .03       0  4999.9     .05       0
Bank Sta=4995.9,4999.9
XS Rating Curve= 0 ,0
Exp/Cntr=0.3,0.1

Type RM Length L Ch R = 1 ,34059   ,435,435,435
BEGIN DESCRIPTION:
BEDFORD CREEK 73.0
END DESCRIPTION:
XS GIS Cut Line= 3
      2848955.65     10212853.11        2848695.       10212807.
      2848455.69     10213003.11
#Sta/Elev= 30
  4735.3 1382.04  4762.3 1379.75  4767.4 1379.91  4775.9 1379.22  4821.5 1377.35
  4826.7  1376.8  4867.3 1374.95  4875.6 1374.19  4880.7 1374.32  4897.8 1373.44
  4934.8 1370.33  4948.5 1369.79    4979 1369.61  4988.8 1368.57  4993.9  1368.7
  4997.1 1368.01  5009.6 1367.14  5009.8 1366.64  5013.3 1366.64  5013.6 1367.14
    5018 1367.19  5032.4 1368.31  5038.8 1369.26  5061.1 1370.67  5096.2 1371.75
    5125 1373.74  5139.3 1373.42  5167.2 1375.52  5281.4 1380.66  5309.4 1382.61
#Mann= 3 ,-1 , 0
  4735.3     .05       0  5009.6     .03       0  5013.6     .05       0
Bank Sta=5009.6,5013.6
XS Rating Curve= 0 ,0
Exp/Cntr=0.3,0.1

Type RM Length L Ch R = 1 ,33624   ,474,474,474
BEGIN DESCRIPTION:
BEDFORD CREEK 72.0
END DESCRIPTION:
XS GIS Cut Line= 3
      2848805.65     10212453.11        2848513.       10212426.
      2848205.69     10212703.11
#Sta/Elev= 30
  4706.1 1374.41  4736.2 1372.27  4806.5 1370.19  4836.6 1368.48  4846.7 1367.37
  4886.8  1365.5    4917 1363.37  4957.1 1362.17  4974.7 1362.76    5000 1362.35
  5003.1 1360.57  5007.9 1360.31  5008.1 1359.81  5011.6 1359.81  5011.9 1360.31
  5024.1 1362.68  5031.5 1363.49  5066.7 1365.06  5074.1  1363.8  5123.5 1367.94
    5187 1370.96  5194.5  1371.7  5229.6 1372.49  5265.4 1375.02  5272.2 1375.01
  5279.2 1376.35  5286.4 1377.02  5321.5 1378.92  5364.1 1382.63  5413.8 1385.32
#Mann= 3 ,-1 , 0
  4706.1     .05       0  5007.9     .03       0  5011.9     .05       0
Bank Sta=5007.9,5011.9
XS Rating Curve= 0 ,0
Exp/Cntr=0.3,0.1

Type RM Length L Ch R = 1 ,33150   ,478,478,478
BEGIN DESCRIPTION:
BEDFORD CREEK 71.0
END DESCRIPTION:
XS GIS Cut Line= 3
      2848655.73     10212003.12      2848518.25       10211966.
       2848205.7      10212203.1
#Sta/Elev= 30
  4857.6 1363.75    4875 1362.28  4888.7  1361.9  4954.8 1357.68  4961.2  1356.7
  4981.9 1355.24  4989.5  1355.8  5006.5 1355.31  5012.8 1353.45    5013 1352.95
  5016.5 1352.95  5016.8 1353.45    5021 1354.11  5028.3 1356.51  5035.6 1356.36
  5078.5  1357.3  5100.1 1356.84  5191.6 1358.91  5199.9 1357.19  5214.5 1358.43
  5249.8 1360.17  5256.1 1359.98  5264.4 1361.31  5285.2 1361.81  5299.8 1362.76
    5306  1362.4  5314.3 1363.29  5342.1 1364.68    5356 1364.83  5392.3  1366.3
#Mann= 3 ,-1 , 0
  4857.6     .05       0  5012.8     .03       0  5016.8     .05       0
Bank Sta=5012.8,5016.8
XS Rating Curve= 0 ,0
Exp/Cntr=0.3,0.1

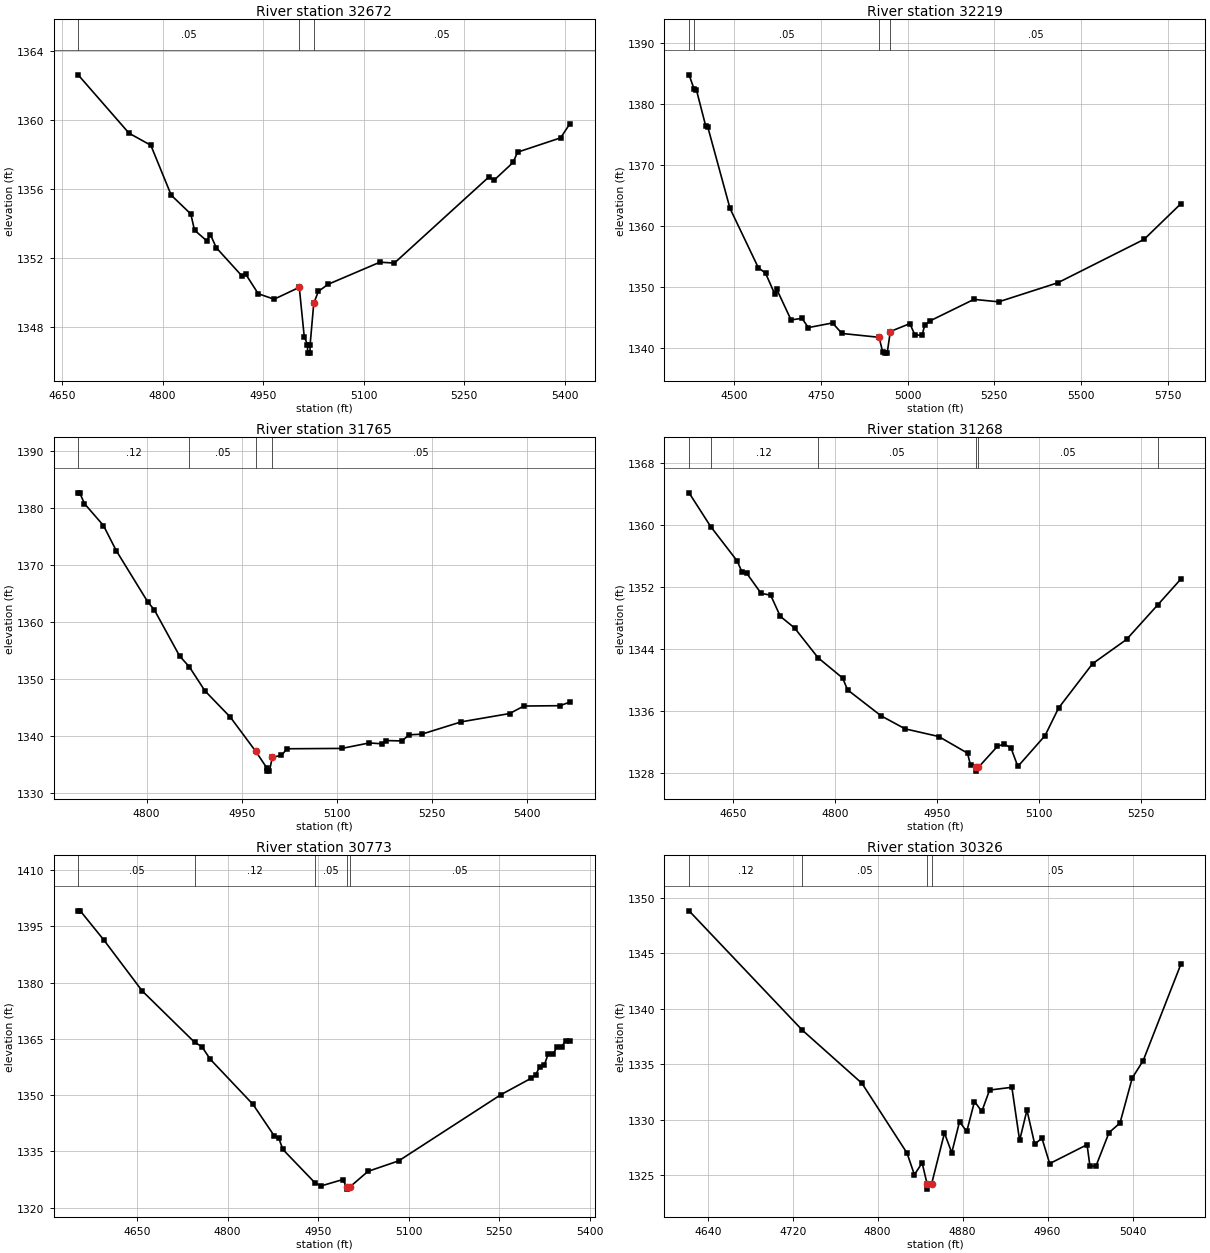
Type RM Length L Ch R = 1 ,32672   ,453,453,453
BEGIN DESCRIPTION:
BEDFORD CREEK 70.0
END DESCRIPTION:
XS GIS Cut Line= 3
      2848655.66      10211653.1      2848355.25       10211527.
      2848055.69     10211803.11
#Sta/Elev= 30
  4674.2 1362.64  4750.1 1359.25  4782.6 1358.55    4813 1355.65  4842.2 1354.56
  4847.7 1353.62    4866    1353  4871.4 1353.36  4880.2  1352.6  4918.9 1350.94
  4924.3 1351.05  4942.7 1349.93  4966.4 1349.61  5003.9  1350.3  5011.3 1347.44
  5016.1 1346.98  5016.4 1346.48  5019.9 1346.48  5020.1 1346.98  5025.5 1349.37
  5032.3 1350.06  5046.5 1350.47  5124.1 1351.76  5145.7 1351.71  5286.9 1356.72
  5294.3 1356.52  5322.6 1357.55  5329.4 1358.15  5393.5 1358.98  5407.4  1359.8
#Mann= 3 , 0 , 0
  4674.2     .05       0  5003.9     .03       0  5025.5     .05       0
Bank Sta=5003.9,5025.5
XS Rating Curve= 0 ,0
Exp/Cntr=0.3,0.1

Type RM Length L Ch R = 1 ,32219   ,454,454,454
BEGIN DESCRIPTION:
BEDFORD CREEK 69.0
END DESCRIPTION:
XS GIS Cut Line= 3
      2848905.65     10210903.12        2848306.       10211094.
      2847705.71     10211603.09
#Sta/Elev= 30
  4370.7 1384.75    4385 1382.46    4392 1382.27    4419 1376.31  4424.3 1376.29
  4488.7 1362.88  4570.1 1353.19    4591 1352.28  4617.6 1348.86  4622.9 1349.69
  4664.5 1344.63    4696 1344.88  4714.3 1343.37    4784 1344.13    4811 1342.41
  4918.1 1341.78 4928.58 1339.34  4935.6 1339.19  4941.4 1339.22  4950.4 1342.73
  5006.7 1344.02  5020.9  1342.2  5041.8 1342.09  5049.5  1343.8  5063.8 1344.44
  5191.2 1347.99  5262.6 1347.59  5432.9 1350.71  5681.2 1357.81  5787.1 1363.64
#Mann= 4 ,-1 , 0
  4370.7     .12       0    4385     .05       0  4918.1     .05       0
  4950.4     .05       0
Bank Sta=4918.1,4950.4
XS Rating Curve= 0 ,0
Exp/Cntr=0.3,0.1

Type RM Length L Ch R = 1 ,31765   ,497,497,497
BEGIN DESCRIPTION:
BEDFORD CREEK 68.0
END DESCRIPTION:
XS GIS Cut Line= 3
      2848855.63     10210753.11      2848547.75       10210750.
      2848105.71      10210903.1
#Sta/Elev= 30
  4692.1 1382.66  4694.6 1382.66  4702.1 1380.76  4732.1 1376.92  4752.1 1372.55
  4802.1 1363.51  4812.1 1362.18  4852.1 1354.07  4867.5 1352.16  4892.1 1347.95
  4932.1 1343.35  4972.1 1337.37  4990.1 1334.38  4990.3 1333.88  4993.8 1333.88
  4998.5 1336.35  5012.8 1336.62  5021.4  1337.8    5108 1337.86  5151.3 1338.82
  5171.5 1338.67  5177.2 1339.24    5203 1339.17  5213.8 1340.24  5234.2 1340.36
  5296.5 1342.52  5372.6 1343.97  5395.2 1345.29  5452.3 1345.35  5467.8 1345.99
#Mann= 4 ,-1 , 0
  4692.1     .12       0  4867.5     .05       0  4972.1     .05       0
  4998.5     .05       0
Bank Sta=4972.1,4998.5
XS Rating Curve= 0 ,0
Exp/Cntr=0.3,0.1

Type RM Length L Ch R = 1 ,31268   ,495,495,495
BEGIN DESCRIPTION:
BEDFORD CREEK 67.0
END DESCRIPTION:
XS GIS Cut Line= 3
      2848755.69     10210553.11       2848459.5       10210262.
      2848455.68     10209953.12
#Sta/Elev= 30
  4584.7 1364.13  4616.5 1359.78  4655.4 1355.35  4662.5 1353.95  4669.5 1353.76
  4690.8 1351.15  4704.9 1350.91  4719.1 1348.18  4740.2 1346.67  4774.7 1342.83
  4810.9 1340.21  4818.1 1338.69  4867.5 1335.33  4902.9 1333.65  4952.4 1332.66
  4994.8 1330.51  4999.2 1328.95  5006.9 1328.69  5007.1 1328.19  5010.9 1328.69
  5038.9  1331.4  5048.9 1331.69  5058.9 1331.16  5068.9 1328.79  5108.9 1332.77
  5128.9 1336.34  5178.9 1342.06  5228.9 1345.19  5275.2 1349.69  5308.9 1352.99
#Mann= 6 ,-1 , 0
  4584.7     .05       0  4616.5     .12       0  4774.7     .05       0
  5006.9     .05       0  5010.9     .05       0  5275.2     .12       0
Bank Sta=5006.9,5010.9
XS Rating Curve= 0 ,0
Exp/Cntr=0.3,0.1

Type RM Length L Ch R = 1 ,30773   ,447,447,447
BEGIN DESCRIPTION:
BEDFORD CREEK 66.0
END DESCRIPTION:
XS GIS Cut Line= 3
      2849205.68      10210403.1       2848890.5       10210085.
      2848605.67      10209853.1
#Sta/Elev= 30
  4552.2 1399.18  4555.7 1399.18  4594.6 1391.44  4658.3 1377.82  4745.1 1364.12
  4757.3 1362.93  4771.4 1359.54  4842.1 1347.52  4877.4  1339.1  4884.5 1338.61
  4891.6  1335.5  4945.1 1326.54  4955.3 1325.79  4990.6 1327.46  4997.7 1325.42
    4998 1324.92    5002 1325.42  5032.6 1329.66  5083.6 1332.47  5253.1 1350.14
  5302.8 1354.48  5310.5 1355.44    5317 1357.47  5324.9 1358.01  5331.4 1361.08
  5339.3  1360.9  5345.7 1362.86  5353.6 1362.87  5360.1 1364.54  5367.3 1364.37
#Mann= 5 ,-1 , 0
  4552.2     .05       0  4745.1     .12       0  4945.1     .05       0
  4997.7     .05       0    5002     .05       0
Bank Sta=4997.7,5002
XS Rating Curve= 0 ,0
Exp/Cntr=0.3,0.1

Type RM Length L Ch R = 1 ,30326   ,478,478,478
BEGIN DESCRIPTION:
BEDFORD CREEK 65.0
END DESCRIPTION:
XS GIS Cut Line= 3
      2849205.66     10209953.09        2848947.       10209678.
       2848905.7     10209603.14
#Sta/Elev= 30
  4622.4 1348.83  4728.9  1338.1  4785.2  1333.3  4827.7 1327.01  4834.6 1325.07
  4841.9 1326.13  4846.5 1324.27  4846.8 1323.77  4850.9 1324.27  4862.9 1328.82
  4869.8 1327.05  4877.1 1329.84  4883.9 1328.96  4891.2 1331.66  4898.1 1330.77
  4905.4 1332.69  4926.4 1332.94  4933.7 1328.15  4940.6 1330.89  4947.9 1327.82
  4954.7 1328.36    4962 1326.07  4997.2 1327.77  4999.9 1325.85  5005.6 1325.85
  5017.9 1328.86  5028.2 1329.72  5039.8 1333.79    5050 1335.33  5085.5 1344.01
#Mann= 4 ,-1 , 0
  4622.4     .12       0  4728.9     .05       0  4846.5     .05       0
  4850.9     .05       0
Bank Sta=4846.5,4850.9
XS Rating Curve= 0 ,0
Exp/Cntr=0.3,0.1

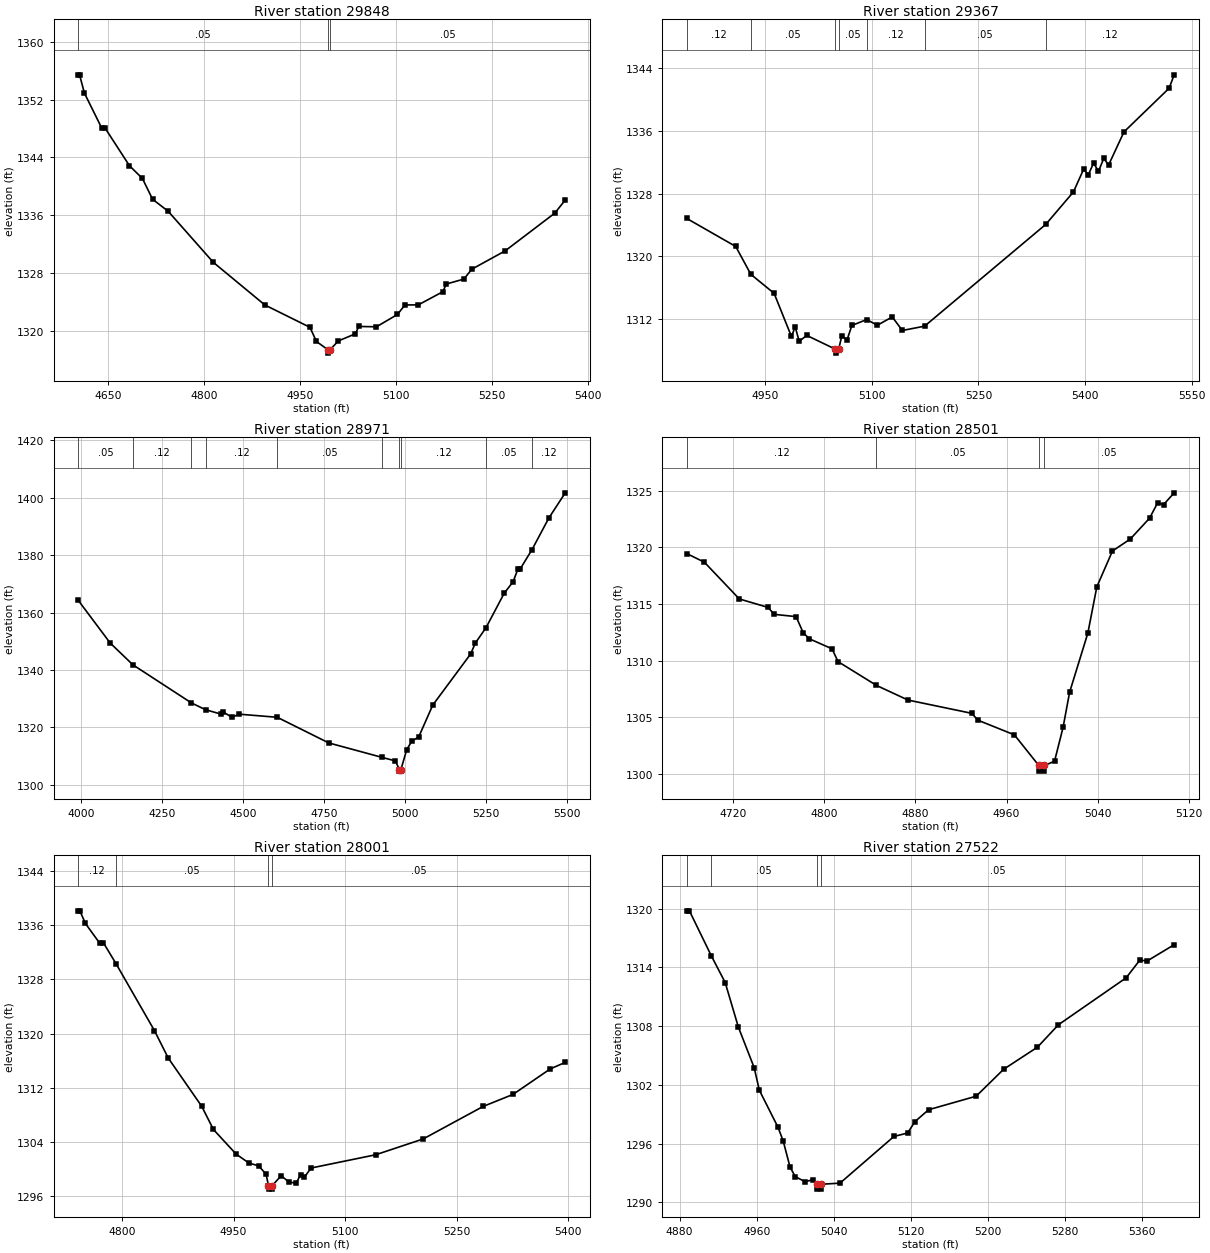
Type RM Length L Ch R = 1 ,29848   ,481,481,481
BEGIN DESCRIPTION:
BEDFORD CREEK 64.0
END DESCRIPTION:
XS GIS Cut Line= 3
      2849455.69     10209953.15        2849405.       10209559.
       2849055.7     10209453.12
#Sta/Elev= 30
  4602.6 1355.46  4605.2 1355.46  4612.7 1352.94  4639.9 1348.07  4644.9  1348.1
  4683.3 1342.85  4703.5 1341.09  4719.4 1338.21  4743.8 1336.54  4814.4 1329.46
    4895 1323.55  4965.6 1320.45  4975.7 1318.49  4993.2 1317.37  4993.5 1316.87
  4997.6 1317.37  5009.7 1318.55  5036.7 1319.55  5041.9 1320.57  5069.6 1320.52
  5102.5 1322.23  5114.2 1323.55  5135.1 1323.56  5173.6 1325.39  5178.8 1326.45
  5206.5 1327.14  5218.7  1328.5    5271 1331.05  5348.6 1336.28    5365  1338.1
#Mann= 3 ,-1 , 0
  4602.6     .05       0  4993.2     .05       0  4997.6     .05       0
Bank Sta=4993.2,4997.6
XS Rating Curve= 0 ,0
Exp/Cntr=0.3,0.1

Type RM Length L Ch R = 1 ,29367   ,396,396,396
BEGIN DESCRIPTION:
BEDFORD CREEK 63.0
END DESCRIPTION:
XS GIS Cut Line= 3
      2849705.65      10209203.1      2849556.75       10209144.
      2849205.68     10208753.11
#Sta/Elev= 30
  4839.8 1324.82  4908.6 1321.25  4929.9 1317.69  4962.6 1315.27  4986.9 1309.78
  4992.3 1310.97  4997.9 1309.15  5008.5  1309.9  5048.9 1308.14  5049.2 1307.64
  5053.4 1308.14  5057.8 1309.81  5065.3 1309.36    5072 1311.17  5092.8 1311.92
  5107.9  1311.2  5128.8 1312.26    5143 1310.53  5174.3 1311.08  5344.7 1324.06
  5383.7 1328.21  5397.9 1331.08  5404.7 1330.42  5412.1 1331.89  5418.9 1330.84
  5426.4 1332.49  5433.1 1331.63  5454.8 1335.87  5518.3 1341.44  5525.4 1343.15
#Mann= 7 ,-1 , 0
  4839.8     .12       0  4929.9     .05       0  5048.9     .05       0
  5053.4     .05       0  5092.8     .12       0  5174.3     .05       0
  5344.7     .12       0
Bank Sta=5048.9,5053.4
XS Rating Curve= 0 ,0
Exp/Cntr=0.3,0.1

Type RM Length L Ch R = 1 ,28971   ,470,470,470
BEGIN DESCRIPTION:
BEDFORD CREEK 62.0
END DESCRIPTION:
XS GIS Cut Line= 3
      2850205.67     10209553.09       2849561.5       10208777.
      2849305.68     10208353.11
#Sta/Elev= 30
  3991.4  1364.4    4091 1349.39    4161 1341.81  4341.7 1328.54  4385.1 1326.18
  4432.2 1324.67  4438.7 1325.44  4467.3 1323.52  4488.2 1324.63  4606.5 1323.54
  4765.5 1314.61  4930.3 1309.57  4971.3 1308.34  4983.1  1305.3  4983.5  1304.8
    4988  1305.3    5006 1312.32  5021.5 1315.19  5042.9 1316.69  5086.3 1327.79
  5203.1 1345.57  5217.5 1349.35  5250.6 1354.73  5306.8 1366.74    5334  1370.7
  5349.5 1375.27  5355.4 1375.05  5392.7 1381.94  5444.6 1392.93  5495.1 1401.67
#Mann= 10 ,-1 , 0
  3991.4     .05       0    4161     .12       0  4341.7     .05       0
  4385.1     .12       0  4606.5     .05       0  4930.3     .12       0
  4983.1     .07       0    4988     .12       0  5250.6     .05       0
  5392.7     .12       0
Bank Sta=4983.1,4988
XS Rating Curve= 0 ,0
Exp/Cntr=0.3,0.1

Type RM Length L Ch R = 1 ,28501   ,500,500,500
BEGIN DESCRIPTION:
BEDFORD CREEK 61.0
END DESCRIPTION:
XS GIS Cut Line= 3
      2849905.67     10209003.15      2850014.75       10208702.
      2850055.67     10208603.14
#Sta/Elev= 30
  4679.7 1319.44  4695.1 1318.68  4725.7 1315.44    4751 1314.69  4756.3 1314.08
  4775.5 1313.88  4781.7 1312.47    4787 1311.93    4807 1311.04  4812.3 1309.91
    4846 1307.81  4873.6 1306.52  4929.5 1305.35    4935 1304.74  4966.9 1303.45
  4988.3 1300.75  4988.7 1300.25  4992.9 1300.25  4993.2 1300.75  5002.1 1301.12
  5009.6 1304.11  5015.3  1307.2  5031.3 1312.42  5039.2 1316.51  5052.9 1319.67
  5068.5 1320.72  5085.4 1322.56  5092.4  1323.9  5097.8 1323.77    5107  1324.8
#Mann= 4 ,-1 , 0
  4679.7     .12       0    4846     .05       0  4988.3     .05       0
  4993.2     .05       0
Bank Sta=4988.3,4993.2
XS Rating Curve= 0 ,0
Exp/Cntr=0.3,0.1

Type RM Length L Ch R = 1 ,28001   ,479,479,479
BEGIN DESCRIPTION:
BEDFORD CREEK 60.0
END DESCRIPTION:
XS GIS Cut Line= 3
      2850255.68     10209353.14      2850294.75       10209097.
      2850255.69     10208703.13
#Sta/Elev= 30
  4740.9 1338.14  4743.5 1338.14    4751 1336.27  4770.2 1333.35  4775.2 1333.41
    4792 1330.35  4843.8 1320.42  4862.3 1316.37  4907.3 1309.23    4923 1305.81
  4953.4 1302.18  4970.8 1300.84  4983.7 1300.44  4993.8 1299.19    4997 1297.49
  4997.3 1296.99  5001.5 1296.99  5001.9 1297.49    5014 1298.97    5024 1298.08
  5034.1 1297.84  5040.1 1299.14  5045.2 1298.75  5054.2 1300.11    5141 1302.07
  5204.9 1304.41  5285.3 1309.21  5325.5 1310.99  5375.7 1314.77  5395.8 1315.73
#Mann= 4 ,-1 , 0
  4740.9     .12       0    4792     .05       0    4997     .05       0
  5001.9     .05       0
Bank Sta=4997,5001.9
XS Rating Curve= 0 ,0
Exp/Cntr=0.3,0.1

Type RM Length L Ch R = 1 ,27522   ,473,473,473
BEGIN DESCRIPTION:
BEDFORD CREEK 59.0
END DESCRIPTION:
XS GIS Cut Line= 3
      2850805.71     10208903.12       2850700.5       10208863.
      2850405.69     10208603.12
#Sta/Elev= 30
  4887.4 1319.77  4890.1 1319.77  4912.9 1315.16  4927.2 1312.45  4940.9 1307.89
  4957.3 1303.75  4962.6 1301.46    4982 1297.67  4987.4 1296.26  4994.5  1293.6
  4999.9 1292.63  5010.2  1292.1  5017.8 1292.31    5022 1291.85  5022.4 1291.35
  5026.6 1291.35    5027 1291.85  5046.3 1291.96  5102.3 1296.73  5116.5 1297.08
  5124.1 1298.25  5138.3 1299.46  5187.6 1300.84  5216.1 1303.59  5251.2 1305.85
    5273 1308.14  5343.2 1312.93  5357.4 1314.74    5365 1314.65    5393 1316.31
#Mann= 4 ,-1 , 0
  4887.4     .12       0  4912.9     .05       0    5022     .05       0
    5027     .05       0
Bank Sta=5022,5027
XS Rating Curve= 0 ,0
Exp/Cntr=0.3,0.1

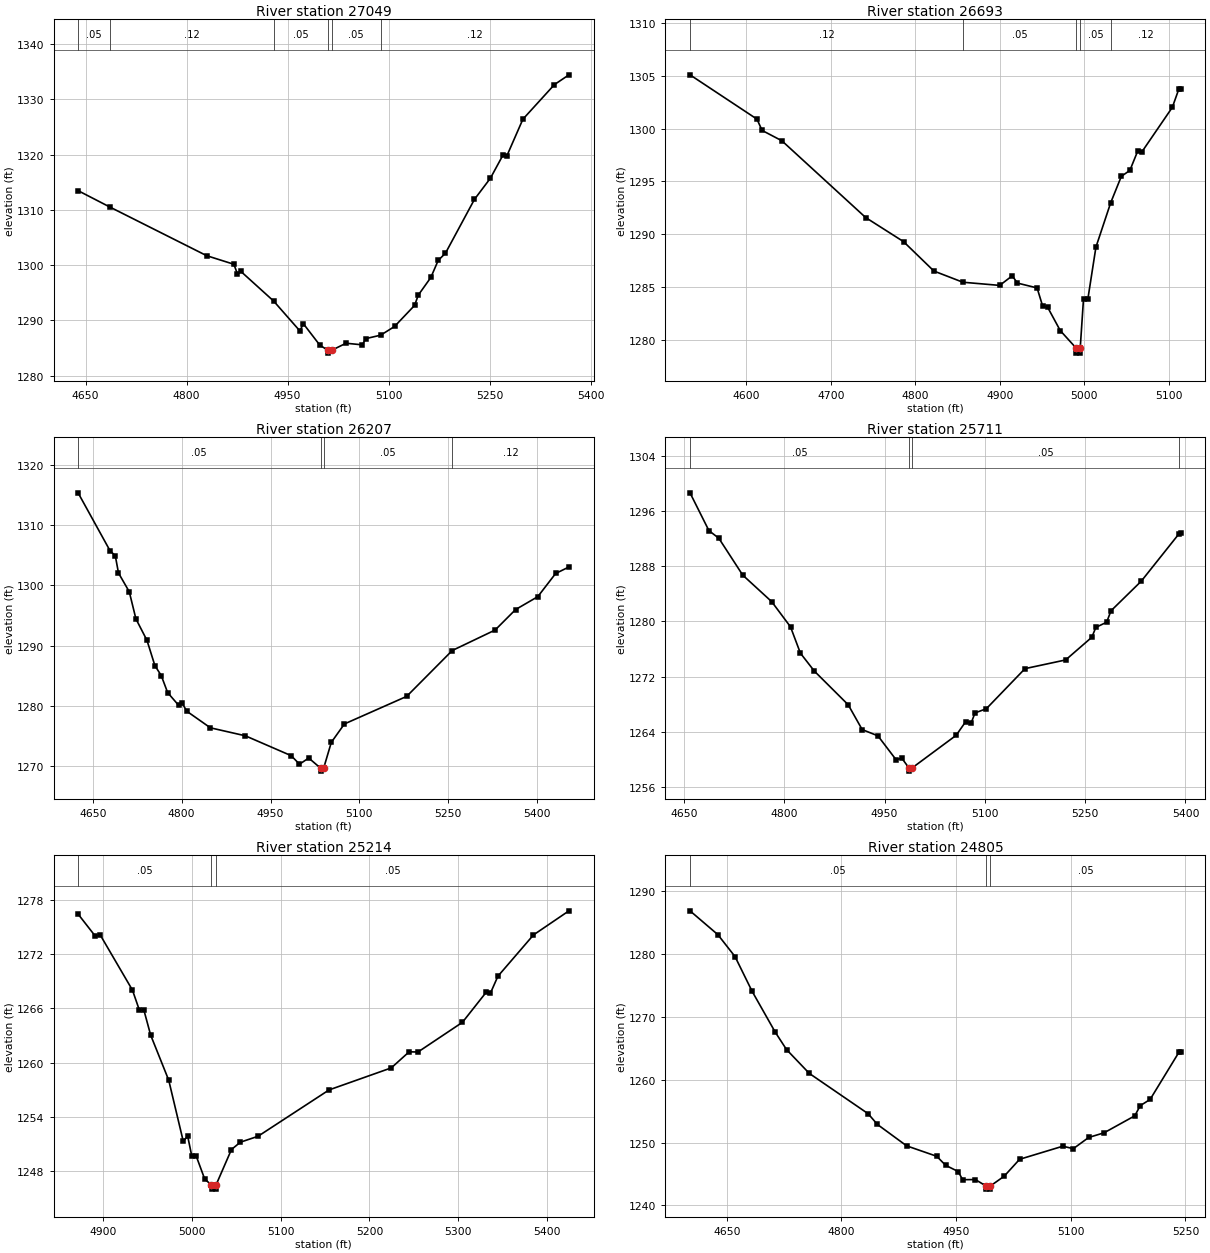
Type RM Length L Ch R = 1 ,27049   ,356,356,356
BEGIN DESCRIPTION:
BEDFORD CREEK 58.0
END DESCRIPTION:
XS GIS Cut Line= 3
      2851005.69     10208903.09      2851043.75       10208544.
      2850905.68      10208203.1
#Sta/Elev= 30
  4638.9 1313.48  4686.5 1310.49  4829.9 1301.71  4870.2 1300.16  4875.6  1298.4
  4880.6 1298.87  4929.3  1293.5  4968.3 1288.09  4973.3 1289.42  4997.9 1285.52
  5010.1 1284.58  5010.5 1284.08  5015.2 1284.58  5036.8 1285.87  5060.9 1285.58
  5066.3 1286.71  5088.2 1287.33  5108.8  1288.9  5138.6 1292.72    5144 1294.57
  5162.7 1297.77  5173.6 1300.85  5184.4 1302.16  5227.5 1311.91  5251.2 1315.74
  5269.9 1319.94  5275.3 1319.69  5299.4 1326.41  5346.2 1332.67  5367.8 1334.44
#Mann= 6 ,-1 , 0
  4638.9     .05       0  4686.5     .12       0  4929.3     .05       0
  5010.1     .05       0  5015.2     .05       0  5088.2     .12       0
Bank Sta=5010.1,5015.2
XS Rating Curve= 0 ,0
Exp/Cntr=0.3,0.1

Type RM Length L Ch R = 1 ,26693   ,486,486,486
BEGIN DESCRIPTION:
BEDFORD CREEK 57.0
END DESCRIPTION:
XS GIS Cut Line= 3
      2851055.68     10208803.12        2851318.       10208417.
      2851305.68     10208303.06
#Sta/Elev= 30
  4533.2 1305.11  4612.5 1300.91  4618.6 1299.84    4642 1298.86  4741.3 1291.58
  4786.1  1289.3  4822.1 1286.51  4856.4 1285.45    4900 1285.15  4914.9 1286.06
    4921 1285.37  4944.3 1284.91  4950.8 1283.21  4956.9 1283.06  4971.8 1280.86
  4990.3 1279.23  4990.7 1278.73    4995 1278.73  4995.4 1279.23  4999.3 1283.89
  5004.5 1283.89    5014 1288.78  5031.5 1292.99  5044.1 1295.49  5054.2 1296.05
  5063.6 1297.91  5068.7 1297.84  5104.5 1302.03    5112 1303.72  5114.6 1303.72
#Mann= 5 ,-1 , 0
  4533.2     .12       0  4856.4     .05       0  4990.3     .05       0
  4995.4     .05       0  5031.5     .12       0
Bank Sta=4990.3,4995.4
XS Rating Curve= 0 ,0
Exp/Cntr=0.3,0.1

Type RM Length L Ch R = 1 ,26207   ,496,496,496
BEGIN DESCRIPTION:
BEDFORD CREEK 56.0
END DESCRIPTION:
XS GIS Cut Line= 3
      2851805.68     10209003.09      2851664.25       10208656.
      2851455.67     10208253.09
#Sta/Elev= 30
  4625.2 1315.32  4679.2 1305.71    4688 1304.89  4693.4 1302.03  4711.6 1298.92
  4722.8 1294.43  4741.5 1290.86  4754.8 1286.69  4765.5 1285.04  4776.4  1282.2
    4795 1280.09  4800.4 1280.53  4808.8 1279.11  4848.5 1276.37  4907.4 1275.05
  4984.9 1271.75  4998.9 1270.34  5014.5 1271.36  5034.4 1269.69  5034.8 1269.19
  5039.7 1269.69  5052.6 1273.96  5074.7 1277.01  5179.8 1281.58  5256.7 1289.18
  5329.1 1292.58  5363.6 1295.97  5401.1 1298.11  5431.2 1301.95  5453.7 1303.03
#Mann= 4 ,-1 , 0
  4625.2     .05       0  5034.4     .05       0  5039.7     .05       0
  5256.7     .12       0
Bank Sta=5034.4,5039.7
XS Rating Curve= 0 ,0
Exp/Cntr=0.3,0.1

Type RM Length L Ch R = 1 ,25711   ,497,497,497
BEGIN DESCRIPTION:
BEDFORD CREEK 55.0
END DESCRIPTION:
XS GIS Cut Line= 3
      2852205.67      10208603.1      2852009.75       10208324.
      2851655.73     10208153.13
#Sta/Elev= 30
    4659 1298.61  4687.3 1293.14  4702.1 1292.04  4737.9  1286.7  4781.2 1282.86
  4809.3 1279.22  4824.1 1275.41    4845 1272.81  4895.6 1267.94  4916.5 1264.35
    4940 1263.45  4967.1    1260  4975.8 1260.21  4986.1 1258.84  4986.5 1258.34
  4991.7 1258.84    5057 1263.52  5071.1 1265.47  5079.6 1265.33  5085.2 1266.76
  5102.2 1267.37    5160 1273.17  5220.8 1274.43  5259.9 1277.71    5266 1279.14
  5282.1 1279.89  5288.6 1281.54  5333.9 1285.83  5389.7 1292.61  5393.1 1292.74
#Mann= 4 ,-1 , 0
    4659     .05       0  4986.1     .03       0  4991.7     .05       0
  5389.7     .12       0
Bank Sta=4986.1,4991.7
XS Rating Curve= 0 ,0
Exp/Cntr=0.3,0.1

Type RM Length L Ch R = 1 ,25214   ,409,409,409
BEGIN DESCRIPTION:
BEDFORD CREEK 54.0
END DESCRIPTION:
XS GIS Cut Line= 3
      2852405.66     10207903.12        2852280.       10207930.
      2851855.73     10207953.11
#Sta/Elev= 30
  4871.5 1276.46  4891.1 1273.99  4896.2 1274.19  4932.8 1268.03  4940.6 1265.81
  4945.7 1265.81  4953.3 1263.05  4973.7 1258.04    4990  1251.3  4995.1 1251.82
  4999.7 1249.63  5004.7 1249.63  5014.3 1247.07  5021.5 1246.47    5022 1245.97
  5026.7 1245.97  5027.2 1246.47  5044.4 1250.36  5054.4 1251.17  5074.4 1251.83
  5154.5 1256.97  5224.6 1259.41  5244.7 1261.19  5254.7 1261.17  5304.8 1264.46
  5331.4 1267.77  5336.4  1267.7  5344.8 1269.57  5384.9 1274.15  5424.9 1276.82
#Mann= 3 ,-1 , 0
  4871.5     .05       0  5021.5     .05       0  5027.2     .05       0
Bank Sta=5021.5,5027.2
XS Rating Curve= 0 ,0
Exp/Cntr=0.3,0.1

Type RM Length L Ch R = 1 ,24805   ,463,463,463
BEGIN DESCRIPTION:
BEDFORD CREEK 53.0
END DESCRIPTION:
XS GIS Cut Line= 3
      2852605.65     10207703.09       2852248.5       10207527.
      2852005.67     10207503.11
#Sta/Elev= 30
  4601.8 1286.83  4638.2 1283.05  4660.7 1279.56  4683.1 1274.03  4713.3 1267.55
  4728.1 1264.78  4757.9 1260.99  4834.8 1254.59    4847 1252.88  4885.2 1249.48
  4924.6 1247.82  4936.2 1246.39  4952.6  1245.4  4958.5  1244.1  4975.1 1244.12
  4989.1  1243.1  4989.6  1242.6  4994.4  1242.6  4994.8  1243.1  5012.9 1244.66
    5033 1247.34  5089.5 1249.42  5103.3 1249.03  5123.4 1250.81  5143.5 1251.55
  5183.7 1254.25  5190.8 1255.86  5203.8 1256.86  5241.5 1264.36    5244 1264.36
#Mann= 3 ,-1 , 0
  4601.8     .05       0  4989.1     .05       0  4994.8     .05       0
Bank Sta=4989.1,4994.8
XS Rating Curve= 0 ,0
Exp/Cntr=0.3,0.1

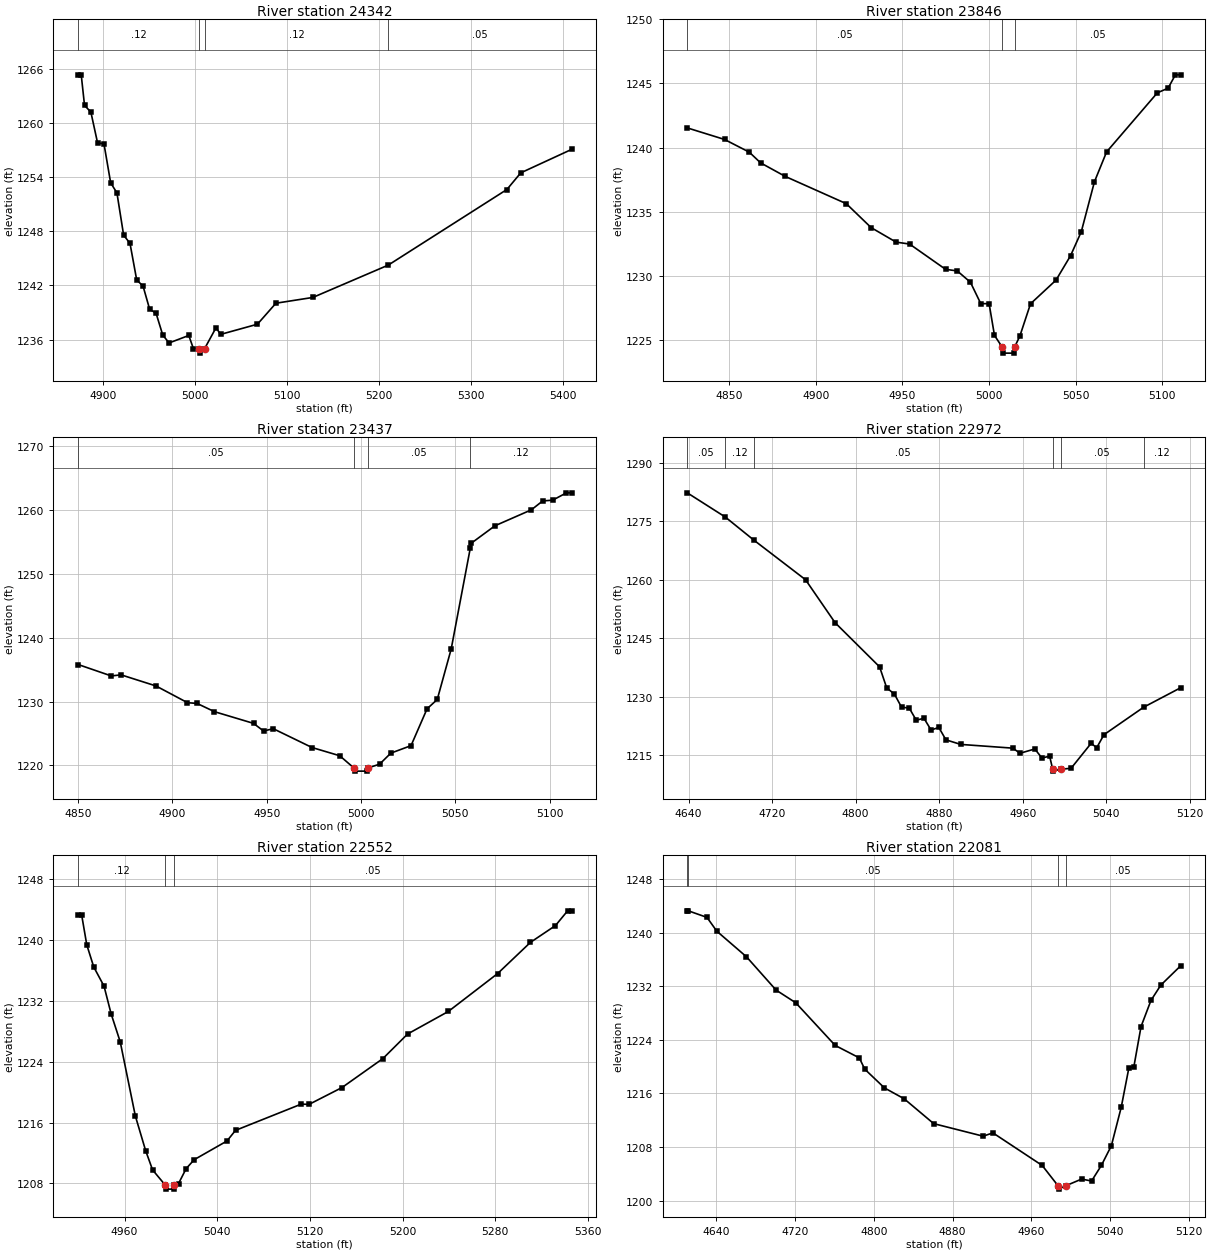
Type RM Length L Ch R = 1 ,24342   ,496,496,496
BEGIN DESCRIPTION:
BEDFORD CREEK 52.0
END DESCRIPTION:
XS GIS Cut Line= 3
      2852655.66     10207303.09       2852563.5       10207216.
      2852155.69     10207253.11
#Sta/Elev= 30
  4873.2 1265.38  4876.6 1265.38  4880.2 1261.99  4887.1 1261.24  4894.4 1257.81
  4901.3 1257.74  4908.6 1253.39  4915.4 1252.28  4922.7 1247.58  4929.6 1246.68
  4936.9 1242.61  4943.8 1241.93    4951 1239.35  4957.9 1238.93  4965.2  1236.5
  4972.1 1235.62  4993.5 1236.45  4998.5    1235    5005 1234.99  5005.4 1234.49
  5010.7 1234.99  5023.1 1237.31  5028.1 1236.57  5068.1  1237.7  5088.2 1240.03
  5128.3 1240.67  5210.3 1244.26  5339.2 1252.65  5354.3  1254.5  5409.5  1257.1
#Mann= 4 ,-1 , 0
  4873.2     .12       0    5005     .07       0  5010.7     .12       0
  5210.3     .05       0
Bank Sta=5005,5010.7
XS Rating Curve= 0 ,0
Exp/Cntr=0.3,0.1

Type RM Length L Ch R = 1 ,23846   ,409,409,409
BEGIN DESCRIPTION:
BEDFORD CREEK 51.0
END DESCRIPTION:
XS GIS Cut Line= 3
      2852605.67      10206953.1       2852471.5       10206842.
      2852405.69     10206753.11
#Sta/Elev= 30
  4825.8 1241.54  4847.3 1240.64  4861.6 1239.65  4868.1 1238.82  4882.4 1237.76
  4917.6 1235.64  4931.9 1233.78  4946.3 1232.65  4954.1  1232.5  4974.9 1230.53
  4981.6 1230.41  4989.2 1229.53  4995.2 1227.86    5000 1227.86  5003.1 1225.39
  5007.4 1224.51  5007.9 1224.01  5014.3 1224.01  5014.8 1224.51  5017.7 1225.32
  5023.9 1227.85  5038.6 1229.69    5047 1231.59  5053.2 1233.46  5060.8 1237.35
  5067.8 1239.67  5097.1 1244.27  5103.3 1244.63  5107.5 1245.67  5110.6 1245.67
#Mann= 3 ,-1 , 0
  4825.8     .05       0  5007.4     .05       0  5014.8     .05       0
Bank Sta=5007.4,5014.8
XS Rating Curve= 0 ,0
Exp/Cntr=0.3,0.1

Type RM Length L Ch R = 1 ,23437   ,465,465,465
BEGIN DESCRIPTION:
BEDFORD CREEK 50.0
END DESCRIPTION:
XS GIS Cut Line= 3
      2852805.69     10206853.09      2852843.75       10206708.
      2852805.68     10206603.09
#Sta/Elev= 30
    4850 1235.81  4867.6 1234.02  4872.8 1234.19  4891.3 1232.45    4908 1229.83
  4913.1 1229.71  4922.3 1228.42    4943 1226.59  4948.3  1225.4  4953.5 1225.75
    4974 1222.81  4988.7 1221.52  4996.2 1219.61  4996.7 1219.11  5003.1 1219.11
  5003.6 1219.61  5009.8 1220.19  5015.8 1221.93  5026.5  1223.1    5035 1228.87
  5040.4 1230.33  5047.8 1238.25  5057.9 1254.02  5058.4  1254.8    5071 1257.54
  5090.3 1260.04  5096.3 1261.43  5101.6 1261.55  5108.9  1262.7  5111.6  1262.7
#Mann= 4 ,-1 , 0
    4850     .05       0  4996.2     .05       0  5003.6     .05       0
  5057.9     .12       0
Bank Sta=4996.2,5003.6
XS Rating Curve= 0 ,0
Exp/Cntr=0.3,0.1

Type RM Length L Ch R = 1 ,22972   ,420,420,420
BEGIN DESCRIPTION:
BEDFORD CREEK 49.0
END DESCRIPTION:
XS GIS Cut Line= 3
      2853555.71     10207003.13       2853289.5       10206759.
      2853255.67     10206653.07
#Sta/Elev= 30
  4638.8 1282.31  4675.1 1276.12  4702.5 1270.19    4752 1260.03  4780.3 1249.01
  4822.9 1237.69  4829.7 1232.31  4837.1  1230.7  4843.9 1227.35  4851.3 1227.11
    4858 1224.01  4865.4  1224.5  4872.2 1221.48  4879.6 1222.16  4886.4 1218.97
  4900.6  1217.8  4950.5 1216.84  4957.3 1215.53  4971.5 1216.63  4978.3 1214.32
  4985.7 1214.77  4988.6 1211.45  4989.1 1210.95  4996.3 1211.45  5006.2 1211.67
  5025.5 1218.11  5030.7 1216.93  5037.7 1220.29  5075.7 1227.34  5111.2 1232.34
#Mann= 6 ,-1 , 0
  4638.8     .05       0  4675.1     .12       0  4702.5     .05       0
  4988.6     .05       0  4996.3     .05       0  5075.7     .12       0
Bank Sta=4988.6,4996.3
XS Rating Curve= 0 ,0
Exp/Cntr=0.3,0.1

Type RM Length L Ch R = 1 ,22552   ,471,471,471
BEGIN DESCRIPTION:
BEDFORD CREEK 48.0
END DESCRIPTION:
XS GIS Cut Line= 3
       2853705.7     10206753.13       2853660.5       10206687.
      2853405.67      10206453.1
#Sta/Elev= 30
  4919.9 1243.29    4923 1243.29  4927.4 1239.38  4933.4 1236.47  4942.3 1233.94
  4948.4 1230.31  4956.3  1226.6  4969.3 1216.88  4978.2 1212.31  4984.2 1209.77
  4995.3 1207.74  4995.8 1207.24  5002.5 1207.24    5003 1207.74  5006.6 1207.97
  5013.2 1209.94  5020.1 1211.11  5048.4 1213.57  5055.8 1214.97  5112.5 1218.42
  5119.3 1218.39  5147.7  1220.6    5183 1224.41  5204.4 1227.65  5239.5 1230.61
  5282.1  1235.6  5310.4  1239.7    5332 1241.91  5342.5 1243.85  5345.9 1243.85
#Mann= 3 ,-1 , 0
  4919.9     .12       0  4995.3     .05       0    5003     .05       0
Bank Sta=4995.3,5003
XS Rating Curve= 0 ,0
Exp/Cntr=0.3,0.1

Type RM Length L Ch R = 1 ,22081   ,410,410,410
BEGIN DESCRIPTION:
BEDFORD CREEK 47.0
END DESCRIPTION:
XS GIS Cut Line= 3
      2853955.68     10206703.14       2853944.5       10206314.
      2853955.69     10206203.06
#Sta/Elev= 30
  4610.7 1243.24  4611.8 1243.24  4630.7 1242.26  4640.7  1240.2  4670.8 1236.38
  4700.8 1231.42  4720.8 1229.52  4760.8 1223.16  4785.3  1221.3  4790.8 1219.62
  4810.8 1216.82  4830.8  1215.2  4860.8 1211.49  4910.9 1209.62  4920.9 1210.11
  4970.9 1205.25    4987 1202.22  4987.5 1201.72  4994.8 1202.22  5010.9 1203.22
    5021 1202.93    5031 1205.27  5041.1  1208.2  5051.1 1213.93  5058.9 1219.84
  5063.9 1219.96  5071.2 1225.97  5081.3 1229.88  5091.3 1232.16  5111.5 1235.05
#Mann= 4 ,-1 , 0
  4610.7     .12       0  4611.8     .05       0    4987     .05       0
  4994.8     .05       0
Bank Sta=4987,4994.8
XS Rating Curve= 0 ,0
Exp/Cntr=0.3,0.1