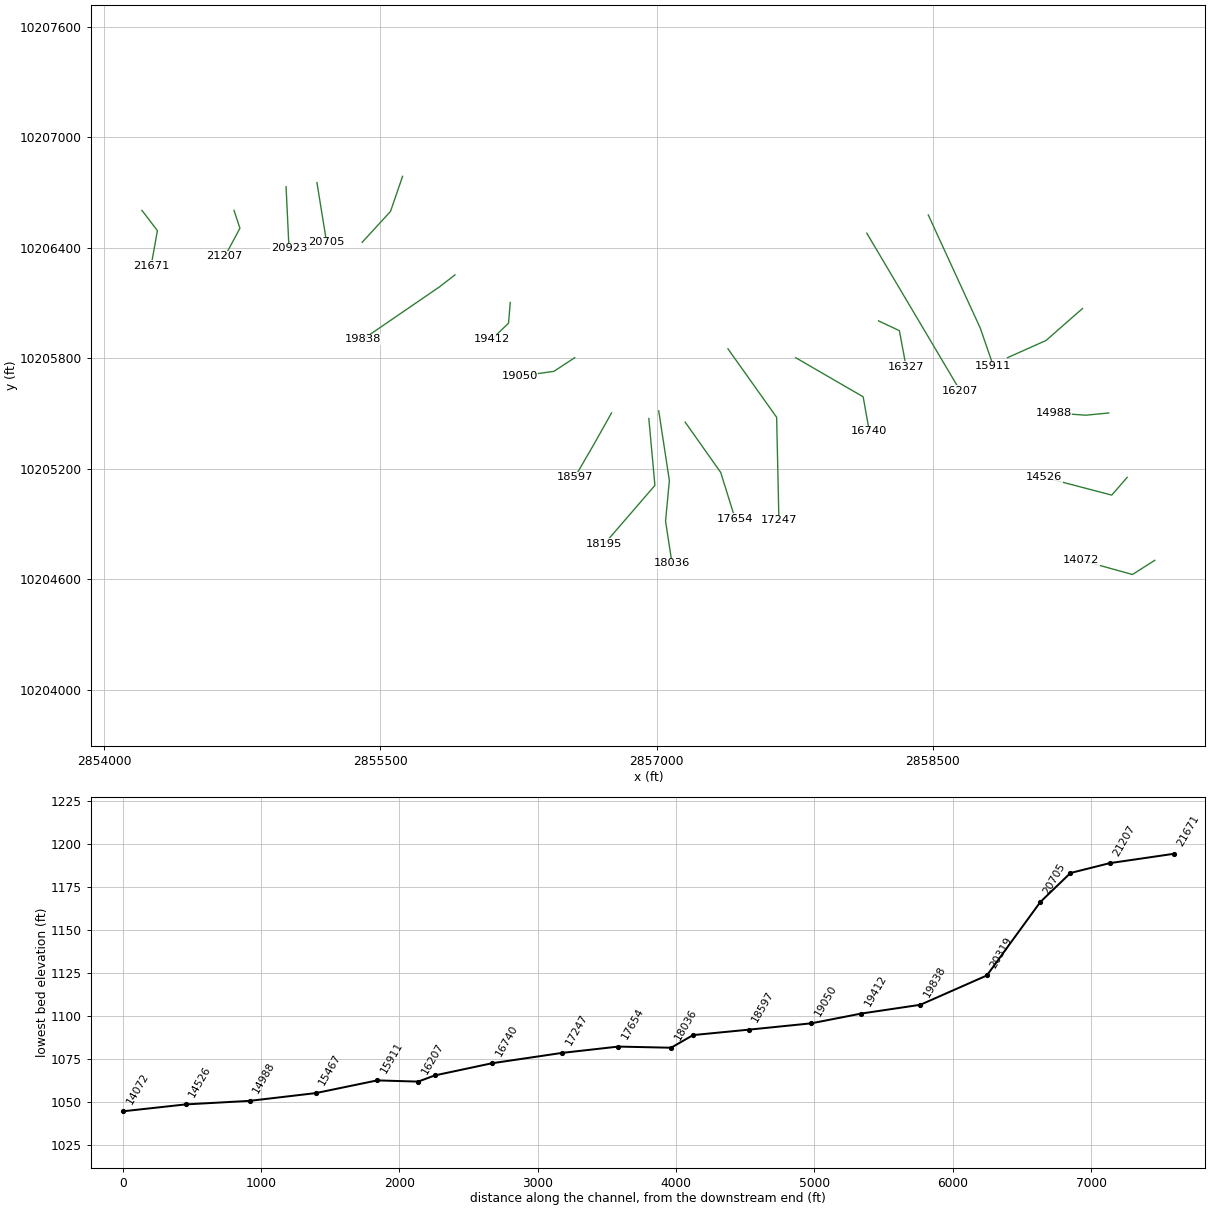
HEC-RAS study BEDFORD CREEK.prj: BEDFORD CREEK Base Level Engineering

--- BEDFORD CREEK.g01 (geometry) --- (continued)

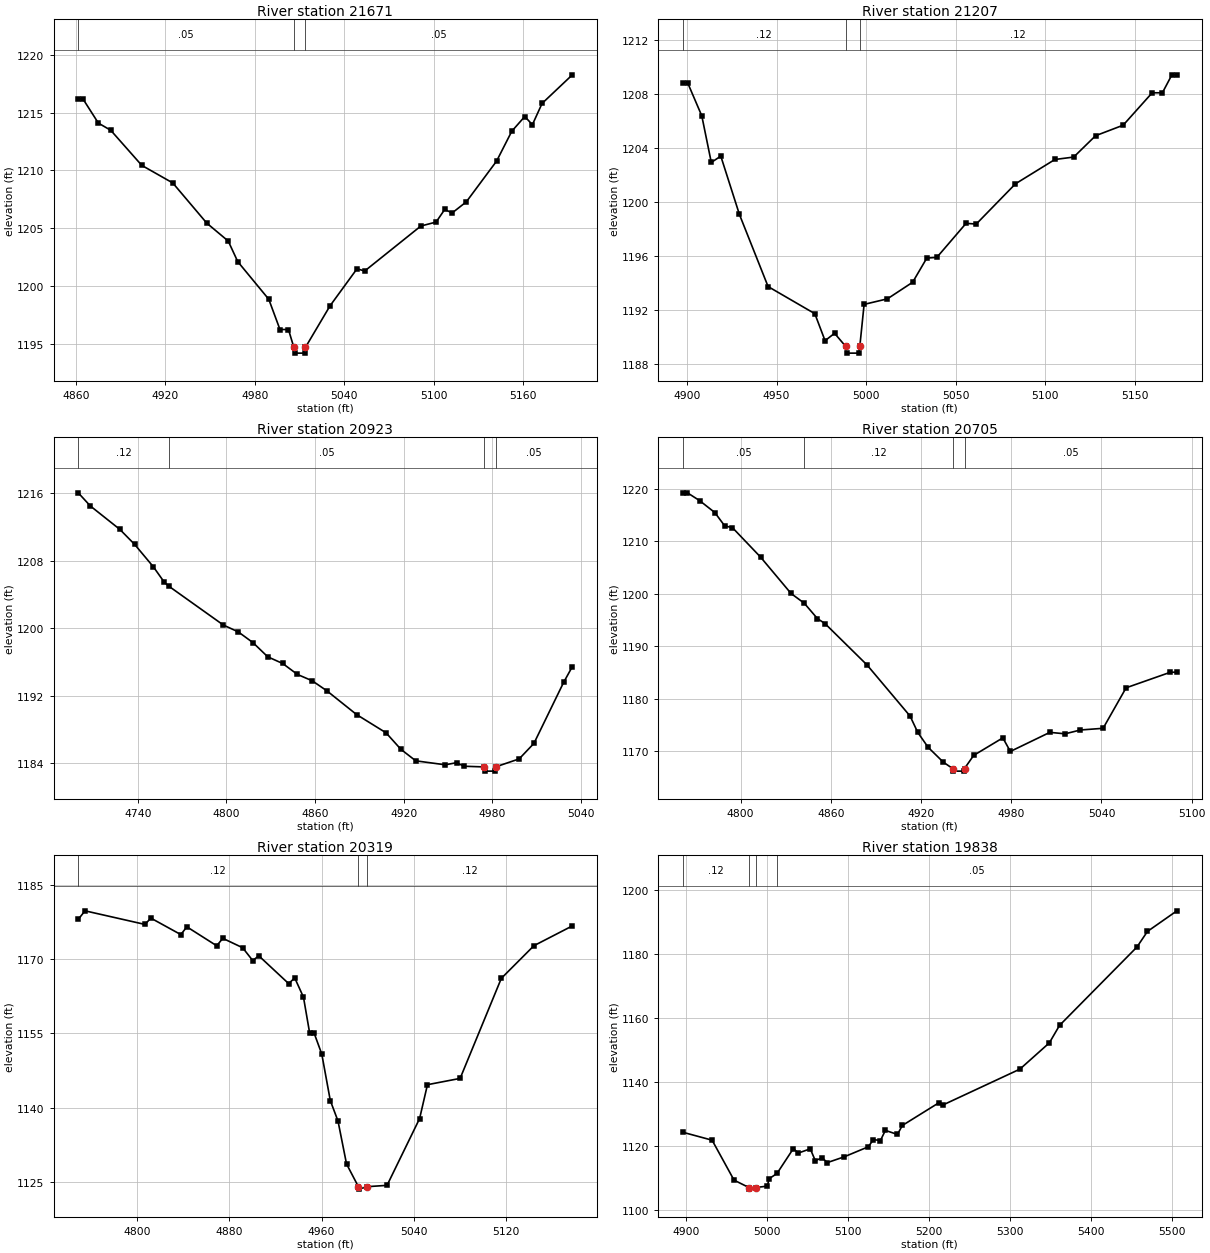
Type RM Length L Ch R = 1 ,21671   ,464,464,464
BEGIN DESCRIPTION:
BEDFORD CREEK 46.0
END DESCRIPTION:
XS GIS Cut Line= 3
       2854205.7     10206603.08      2854289.75       10206493.
      2854255.69     10206303.13
#Sta/Elev= 30
  4861.5 1216.19  4864.6 1216.19    4875 1214.09  4883.3 1213.47  4904.1 1210.44
  4924.9 1208.92  4947.7 1205.45  4962.1  1203.9  4968.5 1202.12  4989.3 1198.87
  4996.8 1196.26  5002.5 1196.26  5006.1 1194.72  5006.6 1194.22  5013.4 1194.22
  5013.9 1194.72  5030.4 1198.31  5048.5 1201.51  5053.6 1201.31  5091.3  1205.2
  5101.5 1205.54  5107.3 1206.63  5112.3 1206.33  5121.8 1207.29  5142.1 1210.81
  5152.3 1213.39    5161 1214.66  5166.1 1213.95  5172.6 1215.79  5192.9 1218.26
#Mann= 3 ,-1 , 0
  4861.5     .05       0  5006.1     .05       0  5013.9     .05       0
Bank Sta=5006.1,5013.9
XS Rating Curve= 0 ,0
Exp/Cntr=0.3,0.1

Type RM Length L Ch R = 1 ,21207   ,284,284,284
BEGIN DESCRIPTION:
BEDFORD CREEK 45.0
END DESCRIPTION:
XS GIS Cut Line= 3
      2854705.67     10206603.14      2854737.75       10206506.
      2854655.69     10206353.13
#Sta/Elev= 30
  4897.7 1208.81  4900.4 1208.81  4908.3 1206.36  4913.6 1202.91  4918.9 1203.38
  4929.3 1199.06  4945.3 1193.72  4971.4 1191.71  4977.1 1189.71  4982.4 1190.26
  4988.6 1189.29  4989.1 1188.79    4996 1188.79  4996.5 1189.29  4998.9  1192.4
  5011.9 1192.81    5026 1194.04  5033.9 1195.83  5039.5 1195.88  5055.8  1198.4
  5061.5 1198.35  5083.4 1201.33  5105.4 1203.13  5115.9 1203.31  5128.1 1204.89
  5143.5 1205.67  5159.7 1208.07  5165.4 1208.07  5170.7  1209.4  5173.5  1209.4
#Mann= 3 ,-1 , 0
  4897.7     .12       0  4988.6     .07       0  4996.5     .12       0
Bank Sta=4988.6,4996.5
XS Rating Curve= 0 ,0
Exp/Cntr=0.3,0.1

Type RM Length L Ch R = 1 ,20923   ,218,218,218
BEGIN DESCRIPTION:
Mapping XS 164903ed
END DESCRIPTION:
XS GIS Cut Line= 2
      2854988.37     10206731.31      2855004.28     10206397.18
#Sta/Elev= 30
  4699.7 1216.05  4707.9 1214.49  4727.9 1211.71  4737.9 1209.93  4750.6 1207.27
    4758 1205.44  4761.2 1204.96    4798 1200.37    4808 1199.57    4818 1198.29
    4828 1196.61  4838.1 1195.82  4848.1 1194.52  4858.1 1193.77  4868.1 1192.57
  4888.1 1189.77  4908.1  1187.6  4918.1 1185.65  4928.2 1184.28  4948.2 1183.81
  4955.8 1184.06  4960.9 1183.64  4974.3 1183.56  4974.8 1183.06  4981.7 1183.06
  4982.2 1183.56  4998.2 1184.51  5008.2 1186.35  5028.3 1193.58  5034.2 1195.45
#Mann= 4 ,-1 , 0
  4699.7     .12       0  4761.2     .05       0  4974.3     .05       0
  4982.2     .05       0
Bank Sta=4974.3,4982.2
XS Rating Curve= 0 ,0
Exp/Cntr=0.3,0.1

Type RM Length L Ch R = 1 ,20705   ,386,386,386
BEGIN DESCRIPTION:
BEDFORD CREEK 44.0
END DESCRIPTION:
XS GIS Cut Line= 2
      2855155.96     10206754.16      2855208.56      10206429.7
#Sta/Elev= 30
  4761.5 1219.23  4764.6 1219.23  4772.7 1217.74  4782.8 1215.47  4789.4 1212.92
  4794.5  1212.6  4813.2 1206.99  4833.5 1200.05  4842.3 1198.19  4851.1 1195.25
  4856.1 1194.31  4884.1 1186.41  4912.7 1176.68  4917.8 1173.57  4924.7 1170.73
  4934.8  1167.9    4941 1166.69  4941.5 1166.19  4948.4 1166.19  4948.9 1166.69
    4955 1169.19  4974.4 1172.53  4979.4 1169.94  5005.7 1173.58  5015.8  1173.3
    5026 1174.03  5041.1 1174.35  5056.4 1182.07  5085.9 1185.04  5090.2 1185.04
#Mann= 4 ,-1 , 0
  4761.5     .05       0  4842.3     .12       0    4941     .05       0
  4948.9     .05       0
Bank Sta=4941,4948.9
XS Rating Curve= 0 ,0
Exp/Cntr=0.3,0.1

Type RM Length L Ch R = 1 ,20319   ,481,481,481
BEGIN DESCRIPTION:
BEDFORD CREEK 43.0
END DESCRIPTION:
XS GIS Cut Line= 3
      2855621.09     10206788.15      2855555.67     10206597.75
      2855401.61     10206429.71
#Sta/Elev= 30
  4748.6 1178.03  4754.5 1179.75  4806.5 1177.01  4811.7 1178.28  4837.7 1174.96
    4843 1176.52  4868.9  1172.7  4874.2  1174.2  4891.4 1172.31  4900.2 1169.72
  4905.5 1170.67  4931.4 1165.07  4936.7 1166.21  4944.3 1162.32  4949.7 1155.04
  4953.6 1155.04  4960.2 1150.85  4967.6 1141.47  4974.3 1137.33  4981.7 1128.68
    4992  1124.1  4992.5  1123.6  4999.9  1124.1  5016.9 1124.36  5045.2 1137.84
    5052 1144.67  5080.4 1145.94  5116.2 1166.13  5144.5 1172.71  5177.9 1176.71
#Mann= 3 ,-1 , 0
  4748.6     .12       0    4992     .07       0  4999.9     .12       0
Bank Sta=4992,4999.9
XS Rating Curve= 0 ,0
Exp/Cntr=0.3,0.1

Type RM Length L Ch R = 1 ,19838   ,426,426,426
BEGIN DESCRIPTION:
BEDFORD CREEK 42.0
END DESCRIPTION:
XS GIS Cut Line= 3
      2855905.66     10206253.09      2855823.25       10206189.
      2855405.65     10205903.09
#Sta/Elev= 30
  4895.6 1124.34  4931.8 1121.86  4958.9 1109.38  4977.3 1107.07  4977.8 1106.57
  4985.8 1107.07    5000 1107.51  5002.3 1109.83    5012 1111.47  5032.2 1119.24
  5038.2 1117.83  5053.1 1119.16  5059.2 1115.51    5068 1116.33  5074.1 1114.85
  5095.1 1116.67  5124.9 1119.81    5131 1122.04  5139.8 1121.76  5145.9 1124.93
  5160.8 1123.65  5166.8 1126.45  5211.6 1133.49  5217.6 1132.93  5312.1 1144.06
  5348.5 1152.27  5361.1 1157.73  5456.7  1182.2  5469.7 1187.08  5506.1 1193.52
#Mann= 4 ,-1 , 0
  4895.6     .12       0  4977.3     .07       0  4985.8     .12       0
    5012     .05       0
Bank Sta=4977.3,4985.8
XS Rating Curve= 0 ,0
Exp/Cntr=0.3,0.1

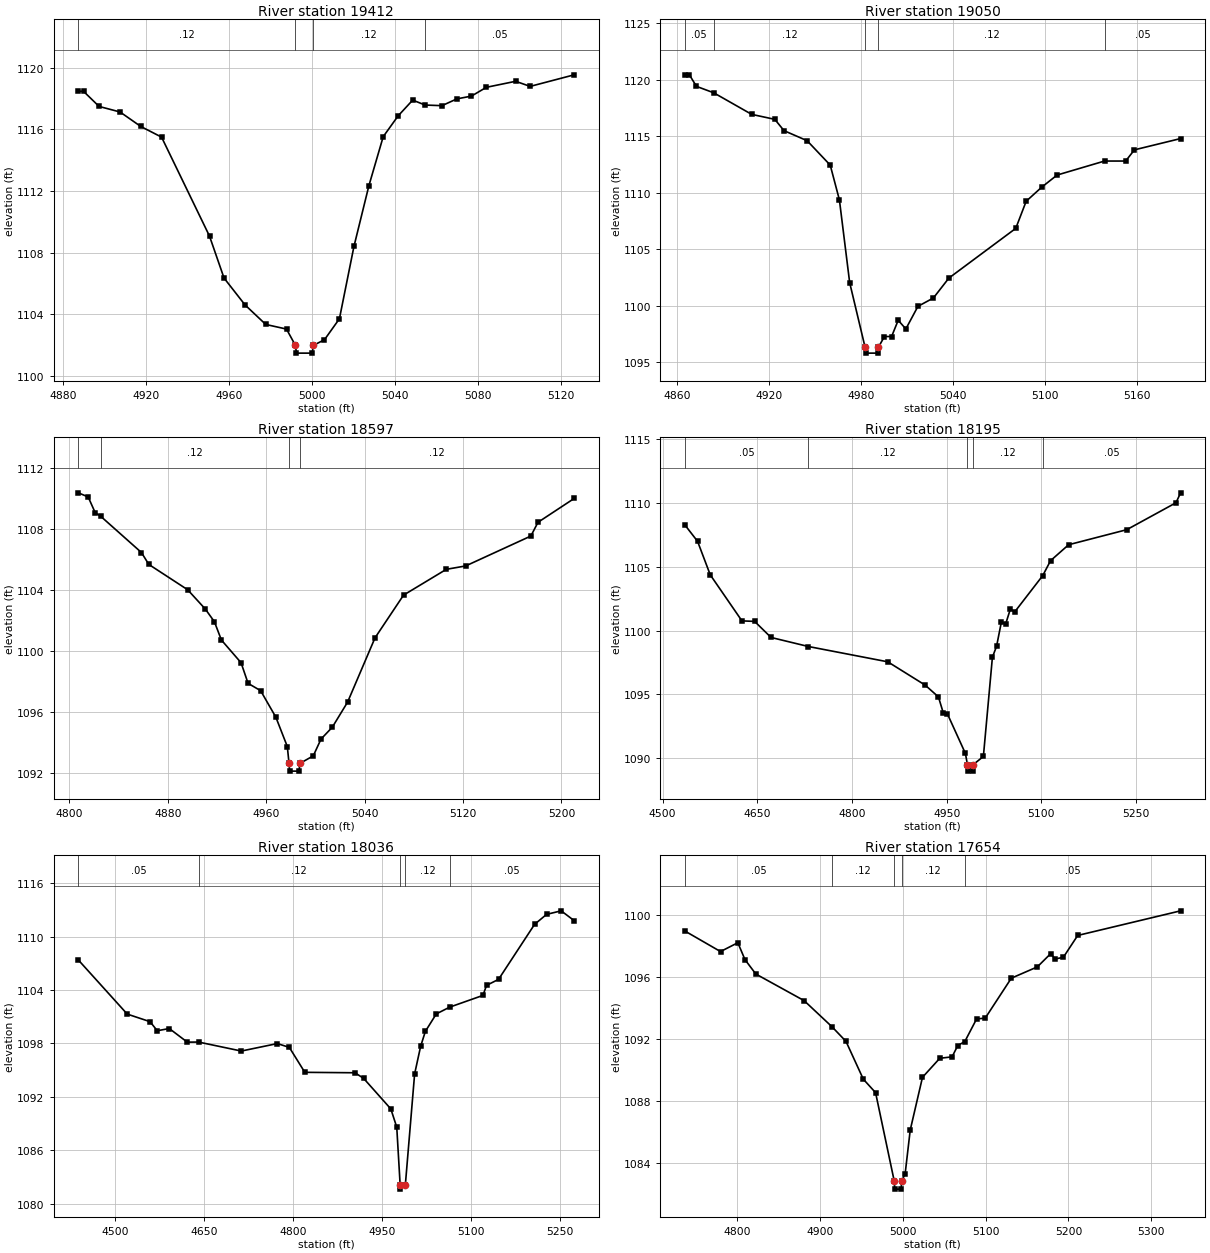
Type RM Length L Ch R = 1 ,19412   ,362,362,362
BEGIN DESCRIPTION:
BEDFORD CREEK 41.0
END DESCRIPTION:
XS GIS Cut Line= 3
      2856205.69     10206103.12       2856196.5       10205991.
      2856105.67      10205903.1
#Sta/Elev= 30
  4887.5 1118.47    4890 1118.47  4897.5 1117.49  4907.6 1117.13  4917.6 1116.19
  4927.6  1115.5  4950.7 1109.08  4957.7 1106.36  4967.8 1104.62  4977.8 1103.35
  4987.8 1103.05  4992.1 1101.99  4992.6 1101.49  5000.2 1101.49  5000.7 1101.99
  5006.1 1102.36  5013.3 1103.72  5020.3 1108.41  5027.5 1112.35  5034.4 1115.53
  5041.6 1116.88  5048.6  1117.9  5054.6 1117.58  5062.7 1117.54  5069.9 1117.98
  5076.9 1118.16  5084.1 1118.73  5098.2 1119.12  5105.2 1118.79  5126.4 1119.54
#Mann= 4 ,-1 , 0
  4887.5     .12       0  4992.1     .07       0  5000.7     .12       0
  5054.6     .05       0
Bank Sta=4992.1,5000.7
XS Rating Curve= 0 ,0
Exp/Cntr=0.3,0.1

Type RM Length L Ch R = 1 ,19050   ,453,453,453
BEGIN DESCRIPTION:
BEDFORD CREEK 40.0
END DESCRIPTION:
XS GIS Cut Line= 3
       2856555.7     10205803.12      2856442.75       10205729.
      2856255.73     10205703.12
#Sta/Elev= 30
  4864.9 1120.44  4867.9 1120.44  4872.5 1119.42  4883.8 1118.85  4908.6 1116.94
  4923.7  1116.5  4929.7  1115.5  4944.8 1114.61  4959.9 1112.45  4965.9 1109.37
  4972.6 1102.05  4982.7 1096.31  4983.2 1095.81  4990.8 1095.81  4991.3 1096.31
  4995.3 1097.28    5000 1097.28  5004.3 1098.72  5009.3 1097.95  5017.2 1099.95
  5027.3 1100.69  5037.4 1102.45  5081.1 1106.85  5087.9 1109.25    5098 1110.49
  5108.1 1111.57  5139.1 1112.81  5152.9 1112.81  5158.6  1113.8  5188.8  1114.8
#Mann= 5 ,-1 , 0
  4864.9     .05       0  4883.8     .12       0  4982.7     .07       0
  4991.3     .12       0  5139.1     .05       0
Bank Sta=4982.7,4991.3
XS Rating Curve= 0 ,0
Exp/Cntr=0.3,0.1

Type RM Length L Ch R = 1 ,18597   ,402,402,402
BEGIN DESCRIPTION:
BEDFORD CREEK 39.0
END DESCRIPTION:
XS GIS Cut Line= 3
      2856755.67     10205503.09      2856661.25       10205335.
      2856555.69     10205153.11
#Sta/Elev= 30
  4807.2 1110.35  4815.2 1110.08  4820.9 1109.05  4825.3 1108.82  4858.5 1106.44
  4864.5 1105.66  4896.1    1104  4910.4 1102.74  4917.8 1101.91  4923.5 1100.71
  4939.5 1099.22  4945.2 1097.87  4955.4 1097.39  4967.8 1095.65  4977.1 1093.73
  4978.5 1092.62    4979 1092.12  4986.7 1092.12  4987.2 1092.62  4998.2 1093.12
  5004.5 1094.22  5013.7    1095  5026.1 1096.64  5048.4 1100.85  5071.6 1103.65
  5106.4 1105.34  5122.1 1105.56  5175.1 1107.52  5180.9 1108.42  5210.3 1109.98
#Mann= 4 ,-1 , 0
  4807.2     .05       0  4825.3     .12       0  4978.5     .07       0
  4987.2     .12       0
Bank Sta=4978.5,4987.2
XS Rating Curve= 0 ,0
Exp/Cntr=0.3,0.1

Type RM Length L Ch R = 1 ,18195   ,159,159,159
BEGIN DESCRIPTION:
BEDFORD CREEK 38.0
END DESCRIPTION:
XS GIS Cut Line= 3
      2856958.24     10205473.25      2856991.29     10205109.73
      2856716.58     10204791.65
#Sta/Elev= 30
  4535.3 1108.29  4555.5    1107  4575.6 1104.37  4625.8 1100.76  4645.9 1100.72
  4671.9 1099.46  4731.1 1098.75  4856.8 1097.55  4916.1 1095.72    4937  1094.8
  4944.6 1093.56  4951.2 1093.47  4979.7 1090.37    4983 1089.48  4983.5 1088.98
  4991.3 1088.98  4991.8 1089.48  5008.2 1090.13  5022.5 1097.91  5029.1 1098.77
  5036.8  1100.7  5043.4  1100.5    5051  1101.7  5057.6 1101.45  5102.2 1104.31
  5114.6 1105.48  5143.2 1106.73  5235.3 1107.91  5313.2 1110.02  5320.6  1110.8
#Mann= 5 ,-1 , 0
  4535.3     .05       0  4731.1     .12       0    4983     .07       0
  4991.8     .12       0  5102.2     .05       0
Bank Sta=4983,4991.8
XS Rating Curve= 0 ,0
Exp/Cntr=0.3,0.1

Type RM Length L Ch R = 1 ,18036   ,382,382,382
BEGIN DESCRIPTION:
Mapping XS 45143ec0
END DESCRIPTION:
XS GIS Cut Line= 4
      2857011.95     10205514.56      2857069.78     10205136.58
      2857049.13     10204915.56       2857084.1     10204687.18
#Sta/Elev= 30
  4438.4 1107.38  4520.8  1101.3  4559.2 1100.45  4571.4 1099.43  4591.6 1099.68
    4622 1098.15    4641 1098.16    4713 1097.15  4773.7 1097.99  4793.9 1097.56
    4820 1094.76  4904.6 1094.71  4919.1 1094.08  4964.9 1090.65  4974.9  1088.6
  4980.6 1082.14  4981.1 1081.64  4989.4 1082.14    5005 1094.58  5015.1 1097.67
  5023.1 1099.36  5041.5 1101.32    5064 1102.08  5120.1  1103.4  5126.2 1104.53
  5146.4  1105.2  5207.1 1111.38  5227.3  1112.5  5251.9  1112.9  5273.8  1111.8
#Mann= 5 ,-1 , 0
  4438.4     .05       0    4641     .12       0  4980.6     .07       0
  4989.4     .12       0    5064     .05       0
Bank Sta=4980.6,4989.4
XS Rating Curve= 0 ,0
Exp/Cntr=0.3,0.1

Type RM Length L Ch R = 1 ,17654   ,407,407,407
BEGIN DESCRIPTION:
BEDFORD CREEK 37.0
END DESCRIPTION:
XS GIS Cut Line= 3
       2857155.7     10205453.09      2857348.65     10205179.96
      2857427.12     10204928.01
#Sta/Elev= 30
    4737 1098.97  4780.1 1097.64    4801 1098.21  4809.6 1097.12  4822.7 1096.19
    4881 1094.47  4914.7 1092.78  4931.5 1091.84  4952.4  1089.4  4967.2 1088.53
  4989.8  1082.8  4990.3  1082.3  4998.1  1082.3  4998.6  1082.8  5002.9  1083.3
    5009 1086.11  5023.8 1089.52  5044.7 1090.75  5059.5 1090.84  5066.4 1091.57
  5074.9 1091.83  5089.1 1093.29  5099.5 1093.34    5131 1095.92  5162.4 1096.65
  5178.6 1097.51  5183.8 1097.16  5193.8 1097.27  5211.1 1098.68  5335.3 1100.27
#Mann= 5 ,-1 , 0
    4737     .05       0  4914.7     .12       0  4989.8     .07       0
  4998.6     .12       0  5074.9     .05       0
Bank Sta=4989.8,4998.6
XS Rating Curve= 0 ,0
Exp/Cntr=0.3,0.1

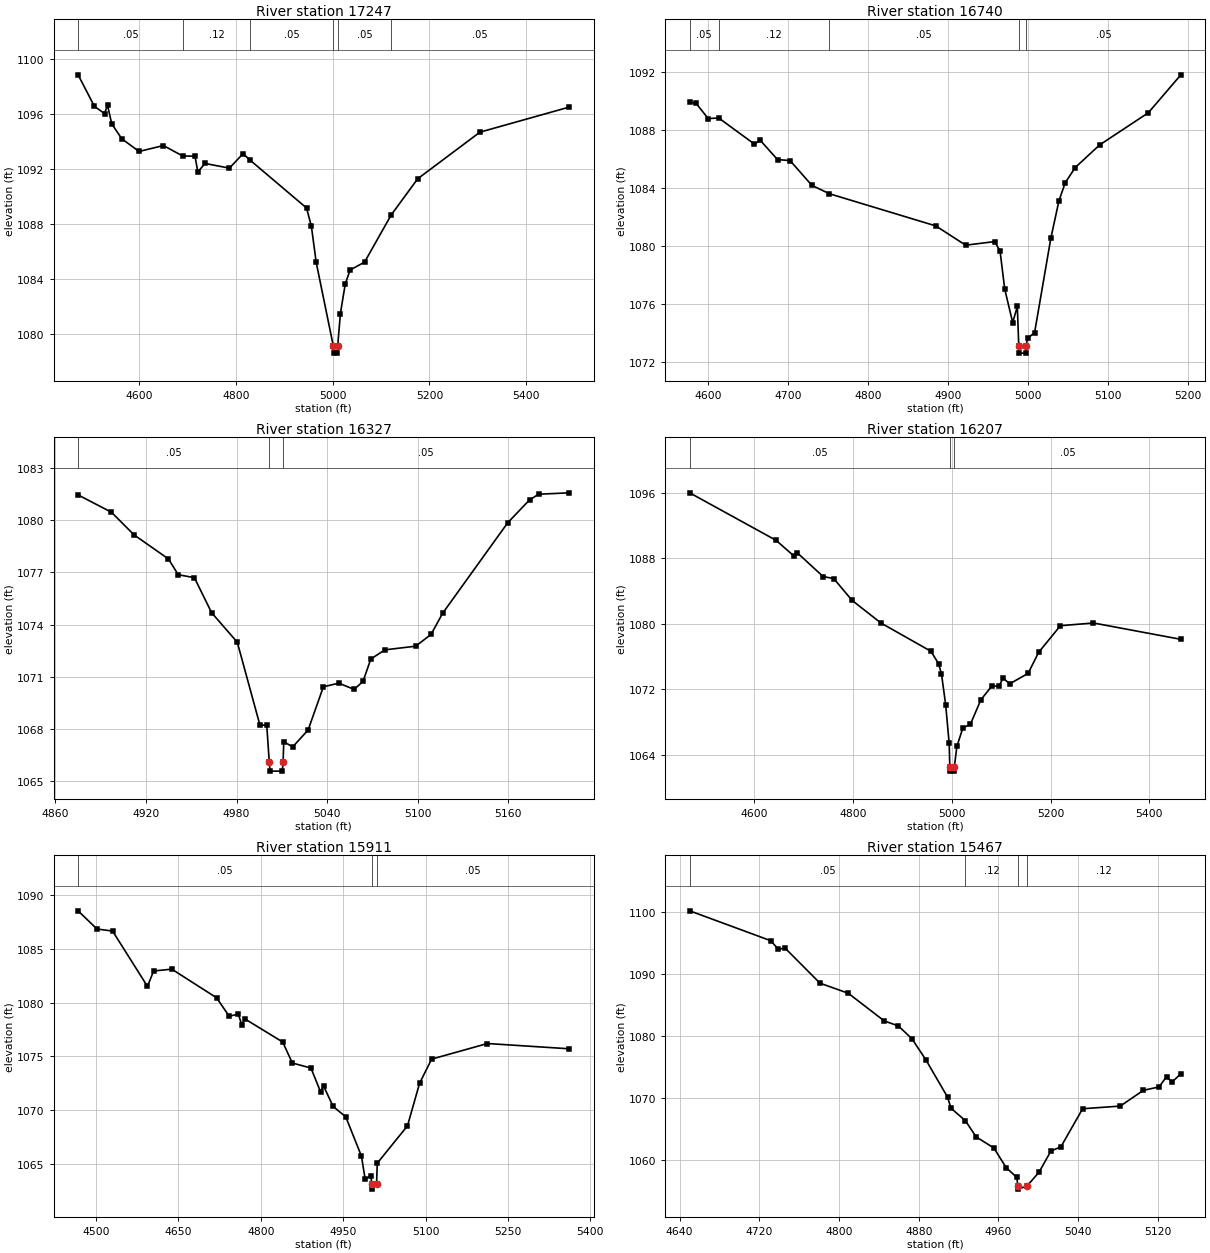
Type RM Length L Ch R = 1 ,17247   ,507,507,507
BEGIN DESCRIPTION:
BEDFORD CREEK 36.0
END DESCRIPTION:
XS GIS Cut Line= 3
      2857387.92     10205851.27       2857652.3     10205479.48
      2857664.69     10204919.72
#Sta/Elev= 30
  4473.1 1098.82  4506.9 1096.53  4527.8 1096.01    4534 1096.62  4542.6 1095.27
  4563.5 1094.18  4599.2 1093.26  4649.6 1093.69  4689.5 1092.93  4714.8 1092.92
  4720.9 1091.78  4735.7 1092.39  4786.1 1092.05  4814.4  1093.1  4828.9 1092.63
  4945.7 1089.16  4955.7 1087.84  4965.7 1085.21  5001.2 1079.13  5001.7 1078.63
  5009.6 1078.63  5010.1 1079.13  5015.7 1081.49  5025.7 1083.63  5035.7 1084.66
  5065.7 1085.23  5120.9 1088.66  5175.7 1091.28  5304.4 1094.66  5489.2 1096.48
#Mann= 6 ,-1 , 0
  4473.1     .05       0  4689.5     .12       0  4828.9     .05       0
  5001.2     .03       0  5010.1     .05       0  5120.9     .05       0
Bank Sta=5001.2,5010.1
XS Rating Curve= 0 ,0
Exp/Cntr=0.3,0.1

Type RM Length L Ch R = 1 ,16740   ,413,413,413
BEGIN DESCRIPTION:
BEDFORD CREEK 35.0
END DESCRIPTION:
XS GIS Cut Line= 3
      2857755.68     10205803.11        2858122.       10205591.
      2858155.69      10205403.1
#Sta/Elev= 30
  4576.7 1089.93  4584.6 1089.86  4599.8  1088.8    4613 1088.84  4657.6 1087.04
  4664.9  1087.3  4686.5 1085.97  4702.2  1085.9  4729.5 1084.19  4751.5 1083.61
  4884.5 1081.39  4921.8 1080.06    4958 1080.31  4964.8 1079.66  4970.6 1077.04
  4980.6 1074.72  4986.4 1075.83  4988.2 1073.11  4988.7 1072.61  4996.7 1072.61
  4997.2 1073.11  4999.2 1073.63    5008 1074.03  5028.3 1080.54  5038.5 1083.14
  5046.4 1084.38  5058.8 1085.42  5089.3 1086.98  5150.2  1089.2  5190.9 1091.82
#Mann= 5 ,-1 , 0
  4576.7     .05       0    4613     .12       0  4751.5     .05       0
  4988.2     .03       0  4997.2     .05       0
Bank Sta=4988.2,4997.2
XS Rating Curve= 0 ,0
Exp/Cntr=0.3,0.1

Type RM Length L Ch R = 1 ,16327   ,120,120,120
BEGIN DESCRIPTION:
BEDFORD CREEK 34.0
END DESCRIPTION:
XS GIS Cut Line= 3
       2858205.7      10206003.1      2858318.75       10205950.
      2858355.68     10205753.13
#Sta/Elev= 30
  4875.1 1081.47  4897.2 1080.47  4912.1 1079.17  4934.9 1077.78  4941.4 1076.87
  4952.1  1076.7  4963.5 1074.68  4980.5 1072.98  4995.5  1068.2    5000  1068.2
  5001.7 1066.05  5002.2 1065.55  5010.3 1065.55  5010.8 1066.05  5011.3 1067.24
  5017.2 1066.95  5027.4 1067.92  5037.5 1070.41  5047.7 1070.62  5057.9 1070.26
  5063.8 1070.73  5068.9 1072.01  5078.2 1072.54  5098.6 1072.75  5108.8 1073.43
  5116.4 1074.64  5159.6 1079.87    5174 1081.18    5180 1081.51  5200.3 1081.59
#Mann= 3 ,-1 , 0
  4875.1     .05       0  5001.7     .05       0  5010.8     .05       0
Bank Sta=5001.7,5010.8
XS Rating Curve= 0 ,0
Exp/Cntr=0.3,0.1

Type RM Length L Ch R = 1 ,16207   ,296,296,296
BEGIN DESCRIPTION:
Mapping XS 6616ceb2
END DESCRIPTION:
XS GIS Cut Line= 2
      2858141.89     10206479.22      2858649.39     10205623.26
#Sta/Elev= 30
  4468.9 1096.03  4643.8 1090.22  4680.8 1088.26  4686.7  1088.7  4739.3 1085.78
  4760.7 1085.54  4797.8 1082.87  4856.3  1080.1  4957.6 1076.64  4973.2 1075.11
    4979 1073.87  4987.5 1070.09  4994.6 1065.36  4995.9 1062.47  4996.4 1061.97
  5004.5 1061.97    5005 1062.47  5010.3 1065.01  5022.4 1067.27  5037.5 1067.69
  5058.9 1070.71  5080.5 1072.34    5096 1072.42  5103.8 1073.35  5117.4 1072.66
  5154.5 1073.93  5175.9 1076.51    5220 1079.77    5287  1080.1    5464  1078.1
#Mann= 3 ,-1 , 0
  4468.9     .05       0  4995.9     .03       0    5005     .05       0
Bank Sta=4995.9,5005
XS Rating Curve= 0 ,0
Exp/Cntr=0.3,0.1

Type RM Length L Ch R = 1 ,15911   ,444,444,444
BEGIN DESCRIPTION:
Mapping XS a0d021f7
END DESCRIPTION:
XS GIS Cut Line= 3
      2858475.77     10206578.12      2858758.03     10205963.97
      2858829.39     10205757.46
#Sta/Elev= 30
  4467.2 1088.53  4501.6 1086.84    4530 1086.65  4593.5 1081.51  4604.8 1082.94
  4637.8 1083.11  4719.4 1080.45  4742.4 1078.73  4758.9 1078.94  4765.3 1077.93
  4770.8 1078.49  4839.8 1076.34  4857.3 1074.39  4891.2 1073.92  4908.7 1071.72
  4914.2 1072.25  4931.7 1070.35  4954.7 1069.38  4983.2 1065.73    4990 1063.58
  5000.6 1063.93  5001.5 1063.17    5002 1062.67  5010.7 1063.17    5012 1065.08
    5067 1068.55    5089  1072.5    5111 1074.75  5212.6  1076.2  5361.6 1075.71
#Mann= 3 ,-1 , 0
  4467.2     .05       0  5001.5     .05       0  5010.7     .05       0
Bank Sta=5001.5,5010.7
XS Rating Curve= 0 ,0
Exp/Cntr=0.3,0.1

Type RM Length L Ch R = 1 ,15467   ,479,479,479
BEGIN DESCRIPTION:
BEDFORD CREEK 32.0
END DESCRIPTION:
XS GIS Cut Line= 3
      2859313.39     10206070.48      2859115.45     10205896.84
      2858905.65      10205803.1
#Sta/Elev= 30
  4650.1 1100.27  4731.5 1095.44  4739.1 1094.05  4745.7 1094.27  4780.9 1088.58
  4809.3 1086.95  4845.4 1082.48  4859.6 1081.67  4873.2  1079.6  4887.1 1076.22
    4909 1070.16  4912.4 1068.38  4926.9 1066.35  4937.7 1063.74  4955.4 1061.96
  4967.9 1058.76  4978.6 1057.18  4979.4  1055.8  4979.9  1055.3  4988.7  1055.8
  5000.8 1058.03  5012.8 1061.47  5022.7 1062.12  5044.6 1068.29  5082.4 1068.72
  5105.6 1071.27  5121.3 1071.81  5128.8 1073.47  5134.3  1072.6  5143.2 1073.94
#Mann= 4 ,-1 , 0
  4650.1     .05       0  4926.9     .12       0  4979.4     .07       0
  4988.7     .12       0
Bank Sta=4979.4,4988.7
XS Rating Curve= 0 ,0
Exp/Cntr=0.3,0.1

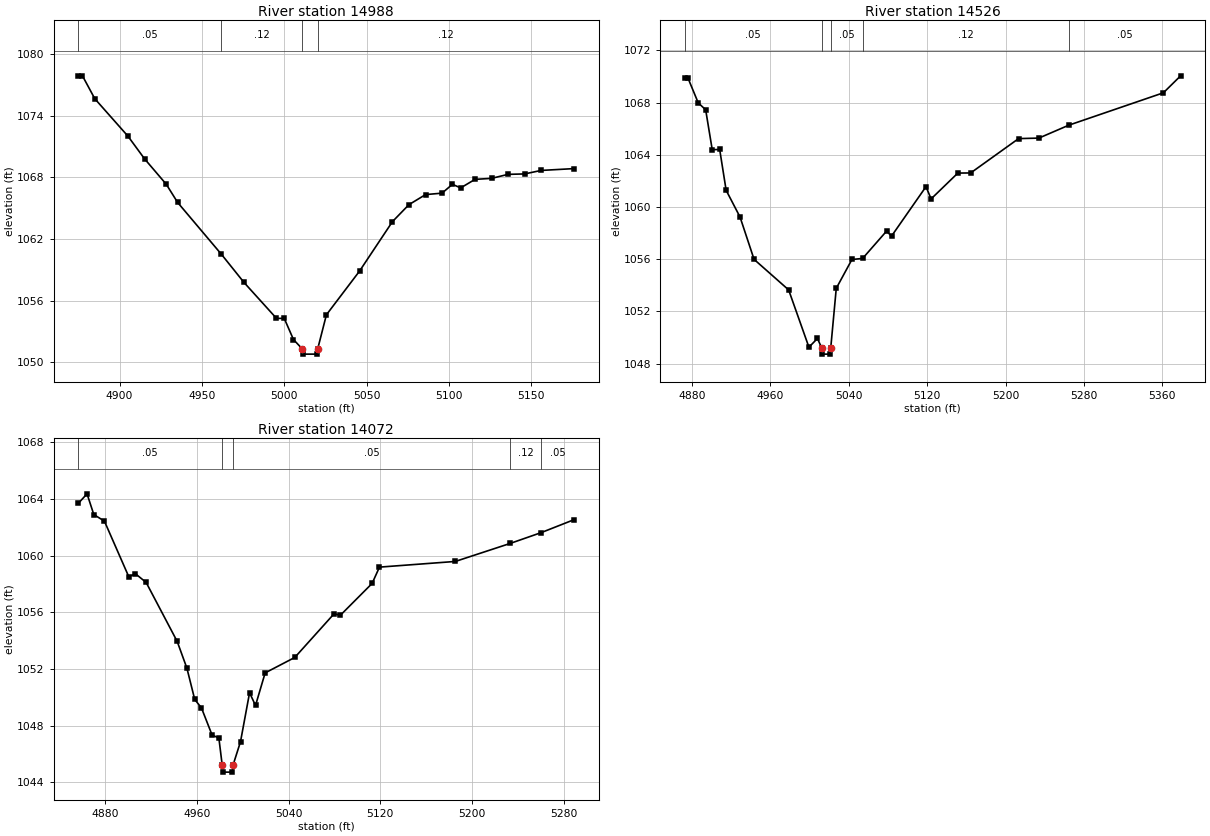
Type RM Length L Ch R = 1 ,14988   ,462,462,462
BEGIN DESCRIPTION:
BEDFORD CREEK 31.0
END DESCRIPTION:
XS GIS Cut Line= 3
      2859455.66     10205503.11      2859331.25       10205491.
      2859155.67     10205503.11
#Sta/Elev= 30
    4875 1077.88  4877.5 1077.88    4885 1075.65  4905.1 1072.01  4915.2  1069.8
  4928.4 1067.32  4935.3 1065.55  4961.9  1060.5  4975.5 1057.78  4995.3 1054.27
    5000 1054.27  5005.6 1052.21    5011 1051.29  5011.5 1050.79  5019.8 1050.79
  5020.3 1051.29  5025.6 1054.62  5045.7 1058.87  5065.7 1063.69  5075.7 1065.34
  5085.8 1066.32  5095.8 1066.46  5102.1 1067.32  5107.1 1066.97  5115.8  1067.8
  5125.9  1067.9  5135.9 1068.29  5145.9 1068.33  5155.9 1068.67    5176 1068.85
#Mann= 4 ,-1 , 0
    4875     .05       0  4961.9     .12       0    5011     .07       0
  5020.3     .12       0
Bank Sta=5011,5020.3
XS Rating Curve= 0 ,0
Exp/Cntr=0.3,0.1

Type RM Length L Ch R = 1 ,14526   ,454,454,454
BEGIN DESCRIPTION:
BEDFORD CREEK 30.0
END DESCRIPTION:
XS GIS Cut Line= 3
      2859555.66     10205153.08        2859472.       10205057.
       2859105.7     10205153.11
#Sta/Elev= 30
  4872.6 1069.87  4875.9 1069.87  4886.3 1067.98  4893.9 1067.45  4900.6 1064.39
  4908.2 1064.41  4914.8 1061.28    4929 1059.23  4943.3 1055.99  4978.6 1053.65
  4999.3 1049.26    5008 1049.93  5012.2 1049.23  5012.7 1048.73  5021.1 1048.73
  5021.6 1049.23  5027.2 1053.77  5043.2 1055.98  5054.1 1056.06  5078.5 1058.15
  5083.6 1057.77  5118.8 1061.56    5124 1060.62  5151.3  1062.6  5164.4 1062.61
  5213.3 1065.24    5234 1065.28  5264.6 1066.27  5361.1 1068.75  5378.7 1070.05
#Mann= 5 ,-1 , 0
  4872.6     .05       0  5012.2     .05       0  5021.6     .05       0
  5054.1     .12       0  5264.6     .05       0
Bank Sta=5012.2,5021.6
XS Rating Curve= 0 ,0
Exp/Cntr=0.3,0.1

Type RM Length L Ch R = 1 ,14072   ,473,473,473
BEGIN DESCRIPTION:
BEDFORD CREEK 29.0
END DESCRIPTION:
XS GIS Cut Line= 3
      2859705.65     10204703.09       2859584.5       10204626.
      2859305.67     10204703.12
#Sta/Elev= 30
  4856.4 1063.69    4864 1064.36  4869.9  1062.9  4879.2 1062.43  4900.4 1058.52
  4906.3 1058.72  4915.6 1058.11  4942.7 1053.95  4951.2 1052.06    4958 1049.86
  4963.9 1049.26  4973.2 1047.34  4979.1 1047.14    4982 1045.23  4982.5 1044.73
    4991 1044.73  4991.5 1045.23    4998 1046.88  5005.9 1050.33  5011.1 1049.43
  5019.5 1051.73  5045.4 1052.82  5079.8 1055.91    5085 1055.78  5112.9 1058.04
  5119.3 1059.19  5185.5 1059.59  5233.4 1060.86  5260.7 1061.63  5289.3 1062.54
#Mann= 5 ,-1 , 0
  4856.4     .05       0    4982     .05       0  4991.5     .05       0
  5233.4     .12       0  5260.7     .05       0
Bank Sta=4982,4991.5
XS Rating Curve= 0 ,0
Exp/Cntr=0.3,0.1