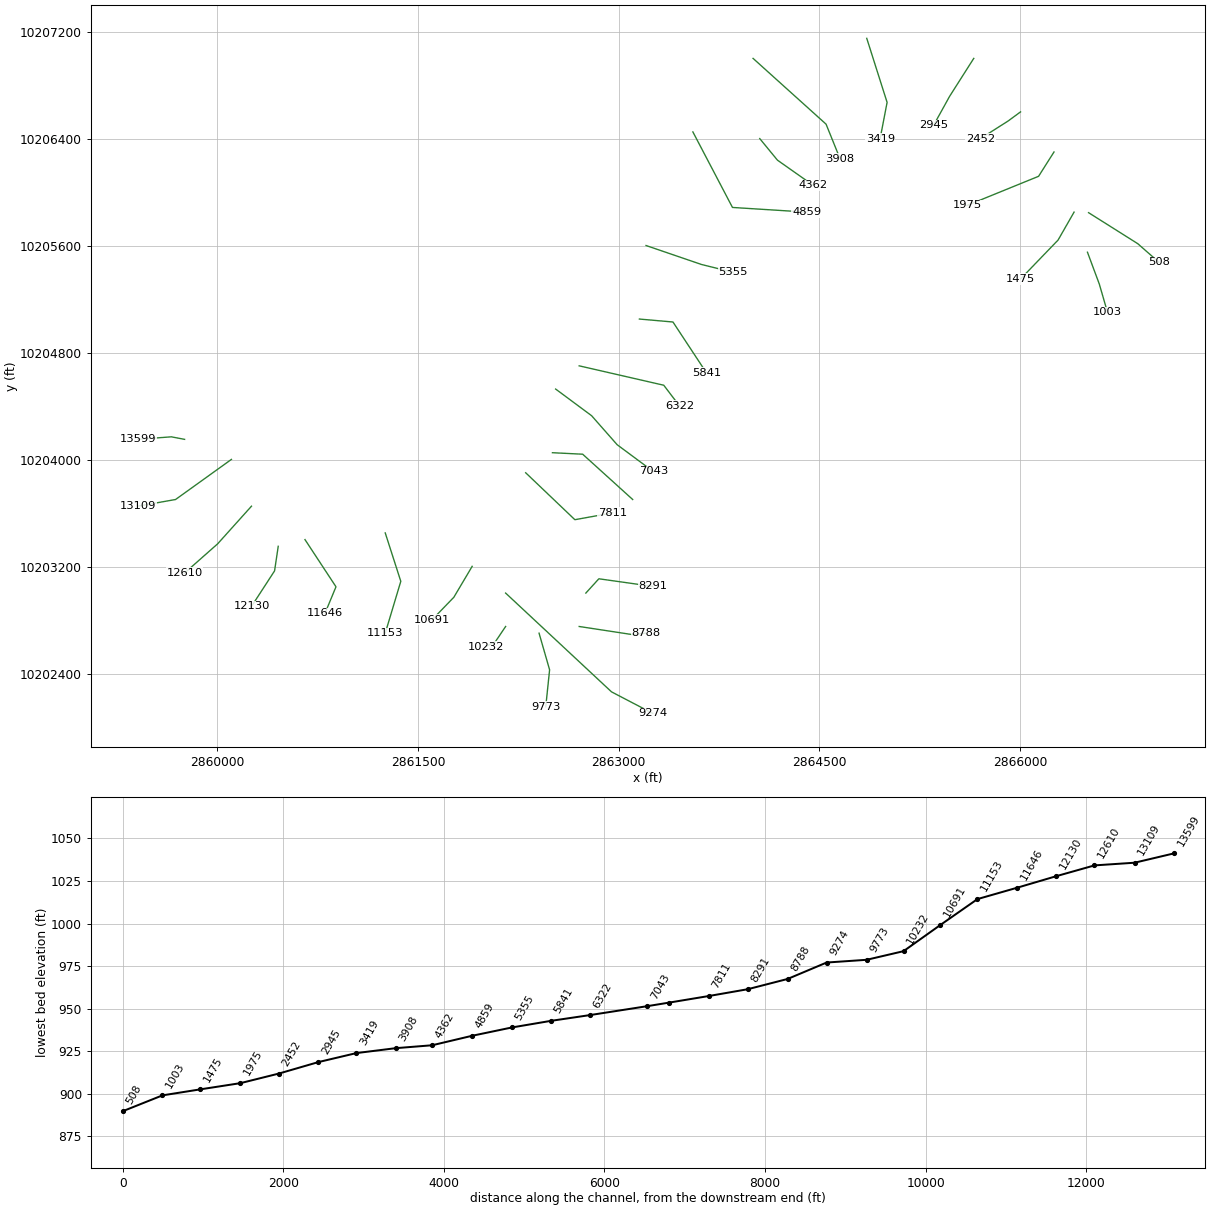
HEC-RAS study BEDFORD CREEK.prj: BEDFORD CREEK Base Level Engineering

--- BEDFORD CREEK.g01 (geometry) --- (continued)

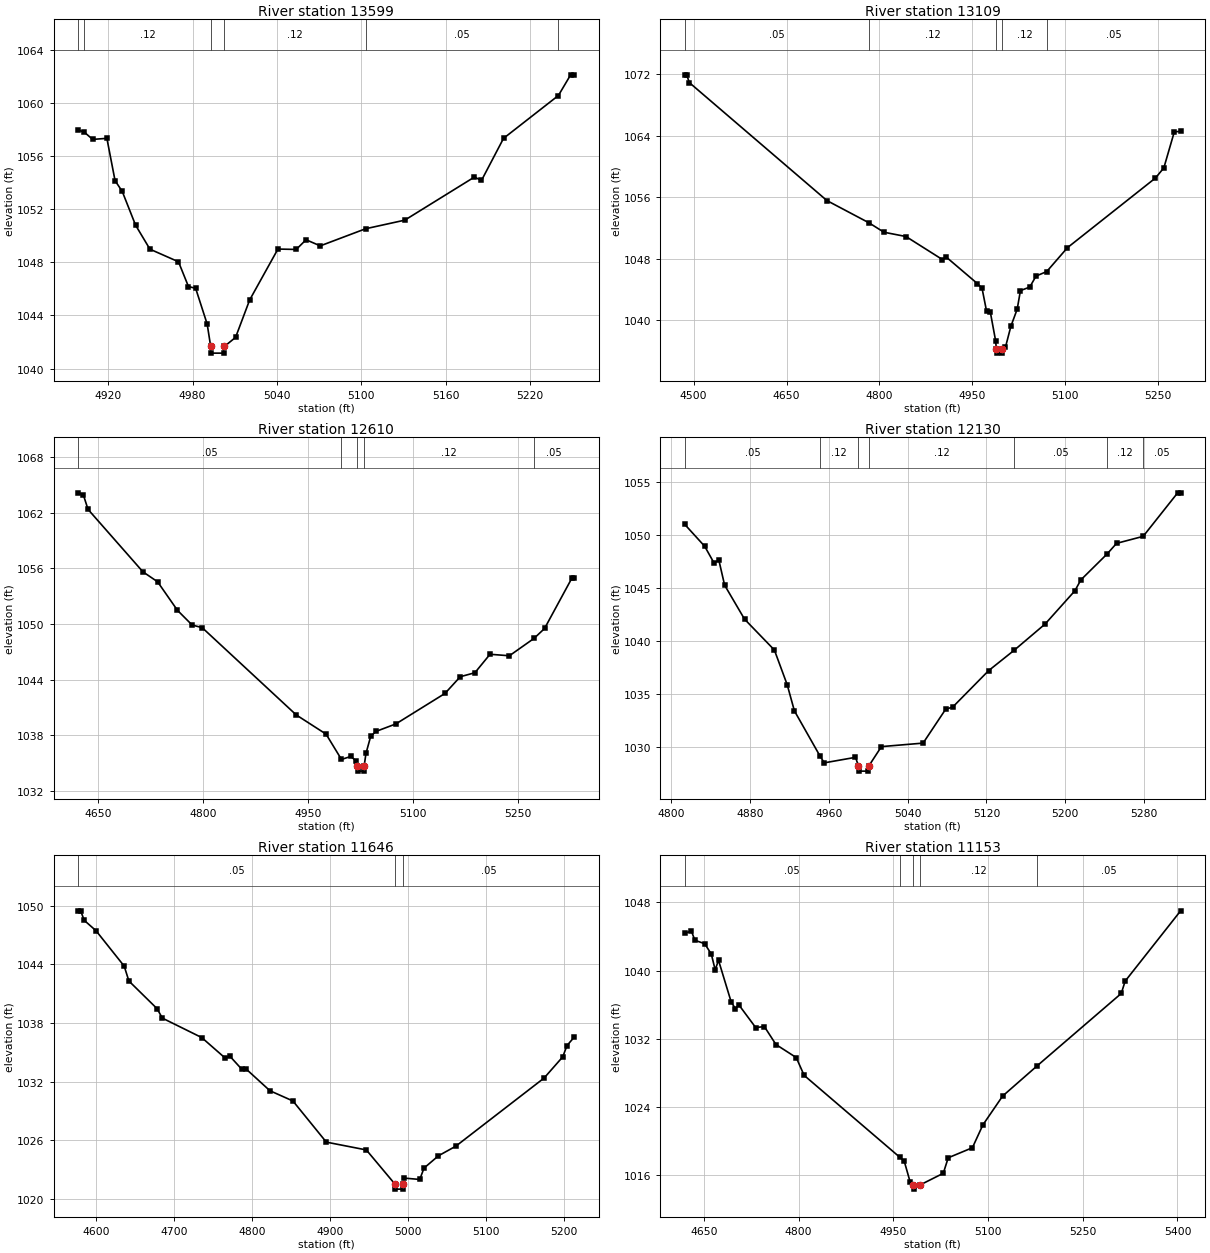
Type RM Length L Ch R = 1 ,13599   ,490,490,490
BEGIN DESCRIPTION:
BEDFORD CREEK 28.0
END DESCRIPTION:
XS GIS Cut Line= 3
      2859755.67     10204153.11      2859656.25       10204172.
      2859405.66     10204153.11
#Sta/Elev= 30
  4898.8 1057.99  4903.1 1057.82    4909 1057.28  4919.1 1057.36  4924.9 1054.17
    4930 1053.36  4939.5 1050.81  4949.7    1049    4970 1048.05  4977.1 1046.18
  4982.2 1046.05  4990.4 1043.35  4992.9 1041.66  4993.4 1041.16  5002.1 1041.16
  5002.6 1041.66  5010.6 1042.35  5020.6 1045.17  5040.7 1049.01  5053.7 1048.98
  5060.7 1049.71  5070.8 1049.25    5103 1050.54  5130.9 1051.19  5180.4 1054.44
  5185.4 1054.18  5201.1 1057.36  5240.1 1060.59  5248.8 1062.15  5251.3 1062.15
#Mann= 6 ,-1 , 0
  4898.8     .05       0  4903.1     .12       0  4992.9     .07       0
  5002.6     .12       0    5103     .05       0  5240.1     .12       0
Bank Sta=4992.9,5002.6
XS Rating Curve= 0 ,0
Exp/Cntr=0.3,0.1

Type RM Length L Ch R = 1 ,13109   ,499,499,499
BEGIN DESCRIPTION:
BEDFORD CREEK 27.0
END DESCRIPTION:
XS GIS Cut Line= 3
      2860105.67      10204003.1        2859688.       10203703.
      2859405.67     10203653.11
#Sta/Elev= 30
  4485.7 1071.92  4488.8 1071.92    4493 1070.91  4715.3 1055.55  4783.1 1052.66
  4807.4 1051.43    4843 1050.87  4901.9 1047.87    4908  1048.2  4958.4 1044.74
  4965.9 1044.13  4973.1 1041.19  4979.2 1041.06  4987.8 1037.31  4989.1 1036.19
  4989.6 1035.69  4998.3 1035.69  4998.8 1036.19  5003.7 1036.45  5012.5 1039.19
  5022.7 1041.42  5027.9 1043.83    5043 1044.29  5053.1 1045.72  5070.4 1046.31
  5103.9 1049.42  5246.1 1058.49  5259.6 1059.81  5276.5  1064.5  5286.7 1064.56
#Mann= 5 ,-1 , 0
  4485.7     .05       0  4783.1     .12       0  4989.1     .07       0
  4998.8     .12       0  5070.4     .05       0
Bank Sta=4989.1,4998.8
XS Rating Curve= 0 ,0
Exp/Cntr=0.3,0.1

Type RM Length L Ch R = 1 ,12610   ,480,480,480
BEGIN DESCRIPTION:
BEDFORD CREEK 26.0
END DESCRIPTION:
XS GIS Cut Line= 3
      2860255.67      10203653.1      2860003.25       10203372.
      2859755.65     10203153.08
#Sta/Elev= 30
  4622.2 1064.13  4629.3 1063.93    4636 1062.35  4714.5 1055.61  4735.4 1054.54
  4763.8 1051.46  4784.8 1049.87    4799  1049.6  4933.5 1040.18  4976.1 1038.11
  4998.1 1035.38  5011.3  1035.7  5018.9 1035.24  5020.6 1034.62  5021.1 1034.12
  5029.9 1034.12  5030.4 1034.62  5033.1 1036.03  5039.8 1037.86  5047.3  1038.4
  5075.8 1039.21    5146  1042.5  5167.8  1044.3  5188.7 1044.73  5210.3 1046.72
    5238 1046.56  5273.3 1048.44  5288.2  1049.5  5327.1 1054.91  5330.5 1054.91
#Mann= 5 ,-1 , 0
  4622.2     .05       0  4998.1     .12       0  5020.6     .07       0
  5030.4     .12       0  5273.3     .05       0
Bank Sta=5020.6,5030.4
XS Rating Curve= 0 ,0
Exp/Cntr=0.3,0.1

Type RM Length L Ch R = 1 ,12130   ,484,484,484
BEGIN DESCRIPTION:
BEDFORD CREEK 25.0
END DESCRIPTION:
XS GIS Cut Line= 3
      2860455.68     10203353.07      2860428.25       10203169.
      2860255.67     10202903.09
#Sta/Elev= 30
  4813.9 1050.97  4834.1 1048.91  4843.5 1047.35  4848.5 1047.59  4854.3 1045.25
  4874.5 1042.05  4904.8 1039.14  4917.8 1035.87  4925.1 1033.41  4951.1 1029.15
  4955.4 1028.51  4987.1 1029.03  4990.1 1028.23  4990.6 1027.73  5000.2 1027.73
  5000.7 1028.23  5013.4 1030.04  5055.7 1030.37  5078.5 1033.55  5085.9 1033.78
  5122.2  1037.2  5148.4 1039.14  5179.5 1041.59  5209.7 1044.72  5215.8 1045.75
  5242.4 1048.19    5252 1049.19    5279 1049.85    5314 1053.95    5317 1053.95
#Mann= 7 ,-1 , 0
  4813.9     .05       0  4951.1     .12       0  4990.1     .07       0
  5000.7     .12       0  5148.4     .05       0  5242.4     .12       0
    5279     .05       0
Bank Sta=4990.1,5000.7
XS Rating Curve= 0 ,0
Exp/Cntr=0.3,0.1

Type RM Length L Ch R = 1 ,11646   ,493,493,493
BEGIN DESCRIPTION:
BEDFORD CREEK 24.0
END DESCRIPTION:
XS GIS Cut Line= 3
      2860655.69     10203403.11       2860887.5       10203050.
      2860805.69     10202853.12
#Sta/Elev= 30
  4577.6 1049.48  4580.6 1049.48  4585.1 1048.51  4600.2 1047.45  4636.4 1043.82
  4642.4  1042.3  4678.5 1039.47  4685.3  1038.5  4735.8 1036.51    4766  1034.4
  4771.9  1034.6    4787 1033.28    4793 1033.27  4823.2 1031.07  4852.7 1030.02
  4895.5 1025.81  4946.8 1025.01  4983.6  1021.5  4984.1    1021  4993.7    1021
  4994.2  1021.5  4995.1 1022.13  5015.3 1021.99  5020.7 1023.15  5039.2 1024.41
  5061.6  1025.4  5174.7 1032.37  5198.6 1034.54    5204 1035.69  5213.2 1036.55
#Mann= 3 ,-1 , 0
  4577.6     .05       0  4983.6     .05       0  4994.2     .05       0
Bank Sta=4983.6,4994.2
XS Rating Curve= 0 ,0
Exp/Cntr=0.3,0.1

Type RM Length L Ch R = 1 ,11153   ,462,462,462
BEGIN DESCRIPTION:
BEDFORD CREEK 23.0
END DESCRIPTION:
XS GIS Cut Line= 3
      2861255.69     10203453.08        2861372.       10203091.
      2861255.67     10202703.07
#Sta/Elev= 30
  4619.7  1044.4  4630.2 1044.63  4635.7 1043.56  4651.2 1043.16  4661.7 1041.94
  4667.8 1040.09  4673.1 1041.21  4693.2 1036.31  4699.9 1035.52  4705.2 1035.99
    4732 1033.31  4745.7 1033.43  4764.1 1031.32  4796.2 1029.79  4808.7  1027.7
  4959.8 1018.11  4967.3 1017.61  4976.8 1015.13  4981.9 1014.84  4982.4 1014.34
  4992.6 1014.84  5029.1  1016.2  5036.9 1018.02  5075.2  1019.2  5091.8 1021.88
  5123.1 1025.27  5178.1 1028.84    5311 1037.32  5317.1 1038.76    5405 1047.02
#Mann= 5 ,-1 , 0
  4619.7     .05       0  4959.8     .12       0  4981.9     .07       0
  4992.6     .12       0  5178.1     .05       0
Bank Sta=4981.9,4992.6
XS Rating Curve= 0 ,0
Exp/Cntr=0.3,0.1

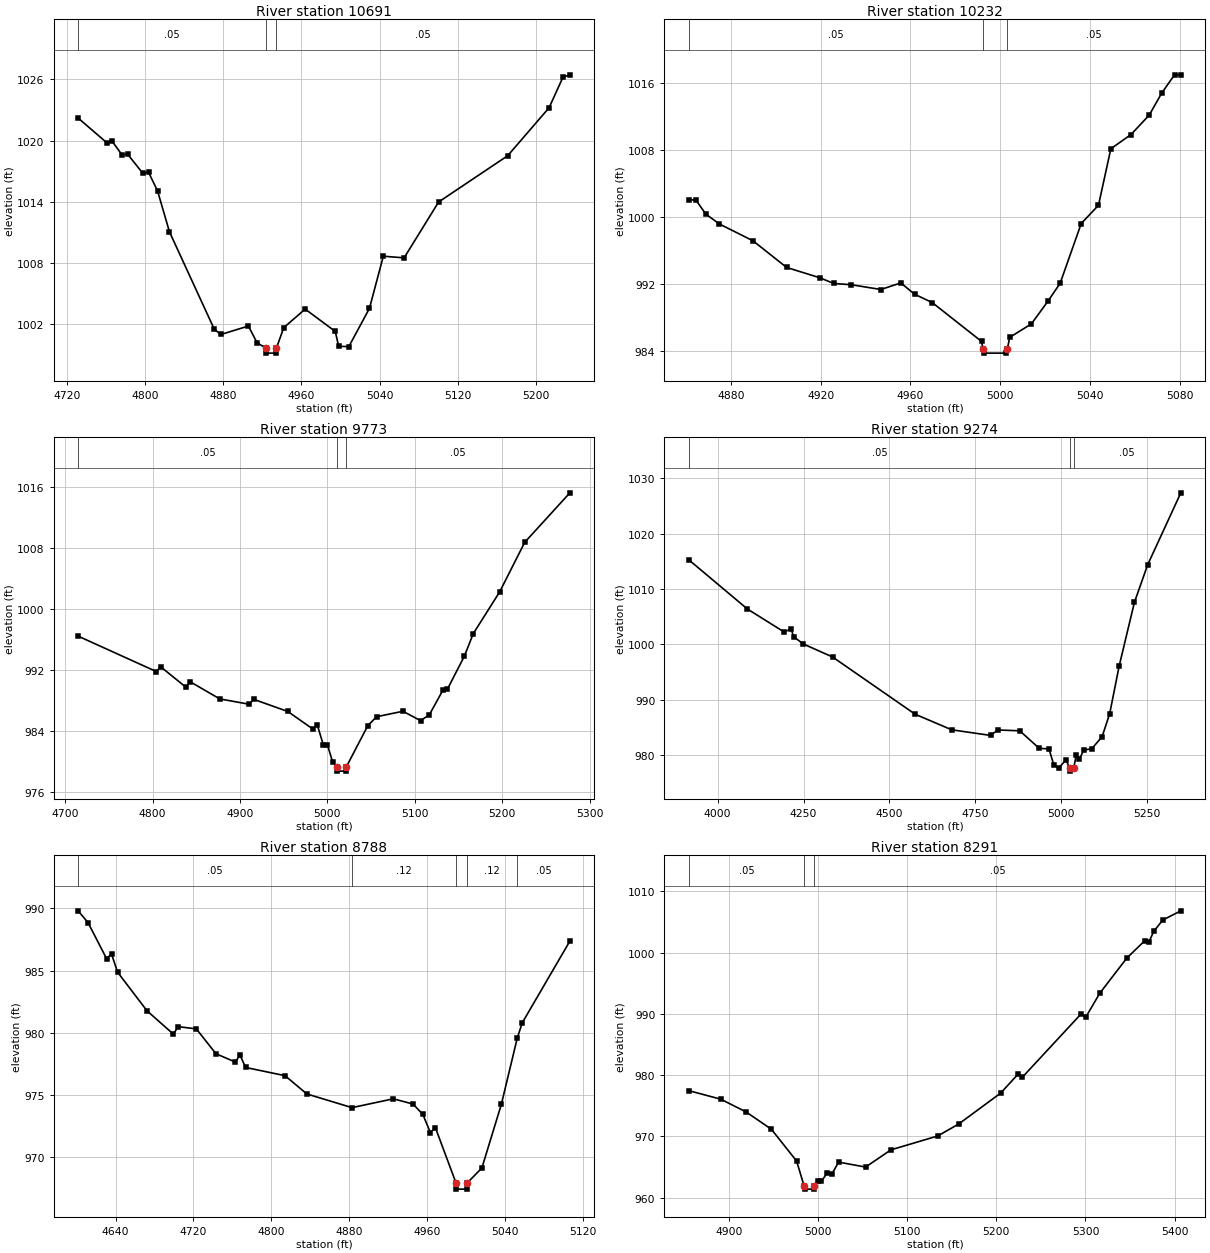
Type RM Length L Ch R = 1 ,10691   ,459,459,459
BEGIN DESCRIPTION:
BEDFORD CREEK 22.0
END DESCRIPTION:
XS GIS Cut Line= 3
      2861905.67     10203203.08      2861768.75       10202972.
      2861605.66     10202803.09
#Sta/Elev= 30
  4731.4 1022.21  4760.6  1019.8  4766.4 1019.91  4776.2 1018.61    4782 1018.67
  4797.7 1016.78  4803.5 1016.88  4812.7 1015.06  4824.9 1011.04  4870.8 1001.48
  4877.6 1000.97  4905.7  1001.8  4914.6 1000.15  4923.6  999.64  4924.1  999.14
  4933.9  999.14  4934.4  999.64  4941.9 1001.64  4963.8 1003.46  4994.6 1001.27
  4998.1  999.81  5008.5  999.78  5029.6 1003.53  5043.8 1008.65  5065.1 1008.49
  5100.4 1013.97  5171.1 1018.51  5213.5 1023.22  5227.7 1026.22  5234.8 1026.45
#Mann= 3 ,-1 , 0
  4731.4     .05       0  4923.6     .05       0  4934.4     .05       0
Bank Sta=4923.6,4934.4
XS Rating Curve= 0 ,0
Exp/Cntr=0.3,0.1

Type RM Length L Ch R = 1 ,10232   ,459,459,459
BEGIN DESCRIPTION:
BEDFORD CREEK 21.0
END DESCRIPTION:
XS GIS Cut Line= 3
      2862155.67     10202753.08      2862078.25       10202638.
       2862005.7     10202603.12
#Sta/Elev= 30
  4861.3 1002.03  4864.3 1002.03  4868.8 1000.33  4874.8  999.16  4889.8  997.15
  4904.8  993.97  4919.7  992.73  4925.8  992.06  4933.6  991.91  4946.8  991.34
  4955.7  992.13  4961.8  990.78  4969.7  989.78  4991.7  985.14  4992.3  984.25
  4992.8  983.75  5002.7  983.75  5003.2  984.25  5004.2  985.63  5013.9  987.24
  5021.2  989.92  5026.7  992.08  5036.1  999.21  5043.8 1001.39  5049.3 1008.13
  5058.3 1009.83  5066.4 1012.14    5072 1014.78  5077.7 1016.95  5080.5 1016.95
#Mann= 3 ,-1 , 0
  4861.3     .05       0  4992.3     .03       0  5003.2     .05       0
Bank Sta=4992.3,5003.2
XS Rating Curve= 0 ,0
Exp/Cntr=0.3,0.1

Type RM Length L Ch R = 1 ,9773    ,499,499,499
BEGIN DESCRIPTION:
BEDFORD CREEK 20.0
END DESCRIPTION:
XS GIS Cut Line= 3
      2862405.69     10202703.09       2862484.5       10202429.
      2862455.68      10202153.1
#Sta/Elev= 30
  4714.8  996.39  4804.2  991.75  4809.4  992.36  4837.9  989.71  4843.1   990.4
  4876.8  988.16  4910.5  987.46  4915.7   988.1  4954.7  986.51  4983.2  984.22
  4988.4  984.75  4995.3  982.13    5000  982.13  5005.9  979.92  5010.5  979.19
    5011  978.69  5020.9  978.69  5021.4  979.19  5046.1  984.63  5056.2  985.82
  5086.4  986.54  5106.5  985.31  5116.5  986.06  5132.3  989.34  5137.3  989.44
  5156.7  993.77  5166.8  996.71    5197 1002.18  5225.7 1008.69  5277.4 1015.18
#Mann= 3 ,-1 , 0
  4714.8     .05       0  5010.5     .05       0  5021.4     .05       0
Bank Sta=5010.5,5021.4
XS Rating Curve= 0 ,0
Exp/Cntr=0.3,0.1

Type RM Length L Ch R = 1 ,9274    ,486,486,486
BEGIN DESCRIPTION:
BEDFORD CREEK 19.0
END DESCRIPTION:
XS GIS Cut Line= 3
      2862155.66     10203003.13       2862947.5       10202264.
      2863255.73     10202103.09
#Sta/Elev= 30
  3916.8 1015.25  4086.6 1006.39  4192.6 1002.27  4214.1 1002.76  4220.9 1001.39
  4249.3 1000.07  4334.3  997.72  4574.6  987.37  4681.1  984.55    4794  983.54
  4815.5  984.52    4879  984.37  4935.7   981.2    4964   981.1  4978.2  978.21
  4992.3  977.66  5013.8  979.11  5024.5  977.58    5025  977.08    5036  977.58
  5043.1  979.92  5052.3  979.21  5065.6  980.92  5088.2   981.1  5118.6   983.3
  5140.7  987.47  5168.4  996.12  5212.6 1007.58  5251.1 1014.38  5347.7  1027.4
#Mann= 3 ,-1 , 0
  3916.8     .05       0  5024.5     .05       0    5036     .05       0
Bank Sta=5024.5,5036
XS Rating Curve= 0 ,0
Exp/Cntr=0.3,0.1

Type RM Length L Ch R = 1 ,8788    ,497,497,497
BEGIN DESCRIPTION:
BEDFORD CREEK 18.0
END DESCRIPTION:
XS GIS Cut Line= 3
      2862705.66     10202753.12       2863099.5       10202693.
      2863205.72     10202703.11
#Sta/Elev= 30
  4601.6   989.8  4611.7  988.86  4630.8  985.96  4635.9  986.33  4642.1  984.87
  4672.4  981.76  4699.4  979.89  4704.4  980.49    4723  980.31  4743.2  978.31
  4762.9  977.65  4767.9   978.2  4773.6  977.21  4814.1  976.55  4836.5  975.08
  4882.9  973.98  4925.3  974.69  4945.6  974.27  4955.7  973.43  4963.4  971.97
  4968.5  972.38  4989.7  967.93  4990.2  967.43  5000.8  967.43  5001.3  967.93
  5016.3  969.13  5036.3  974.25  5052.6  979.56  5057.7  980.79  5106.7  987.37
#Mann= 5 ,-1 , 0
  4601.6     .05       0  4882.9     .12       0  4989.7     .07       0
  5001.3     .12       0  5052.6     .05       0
Bank Sta=4989.7,5001.3
XS Rating Curve= 0 ,0
Exp/Cntr=0.3,0.1

Type RM Length L Ch R = 1 ,8291    ,480,480,480
BEGIN DESCRIPTION:
BEDFORD CREEK 17.0
END DESCRIPTION:
XS GIS Cut Line= 3
      2862755.67      10203003.1      2862852.75       10203110.
      2863255.65     10203053.12
#Sta/Elev= 30
  4855.6  977.47  4891.1  976.09  4919.5  974.01  4947.9  971.18  4976.2  965.99
  4984.6  961.91  4985.1  961.41  4995.7  961.41  4996.2  961.91    5000   962.7
    5004   962.7  5010.8  964.11  5015.8  963.87  5023.2  965.82  5053.5  965.01
  5081.9  967.82  5134.3  970.08    5158  972.05  5204.9  977.08  5224.1  980.12
  5229.1  979.65  5295.2  990.02  5300.3  989.47    5316  993.37  5346.3  999.11
  5366.3 1001.93  5371.4 1001.82  5376.6 1003.49  5386.7 1005.33  5406.9 1006.83
#Mann= 3 ,-1 , 0
  4855.6     .05       0  4984.6     .05       0  4996.2     .05       0
Bank Sta=4984.6,4996.2
XS Rating Curve= 0 ,0
Exp/Cntr=0.3,0.1

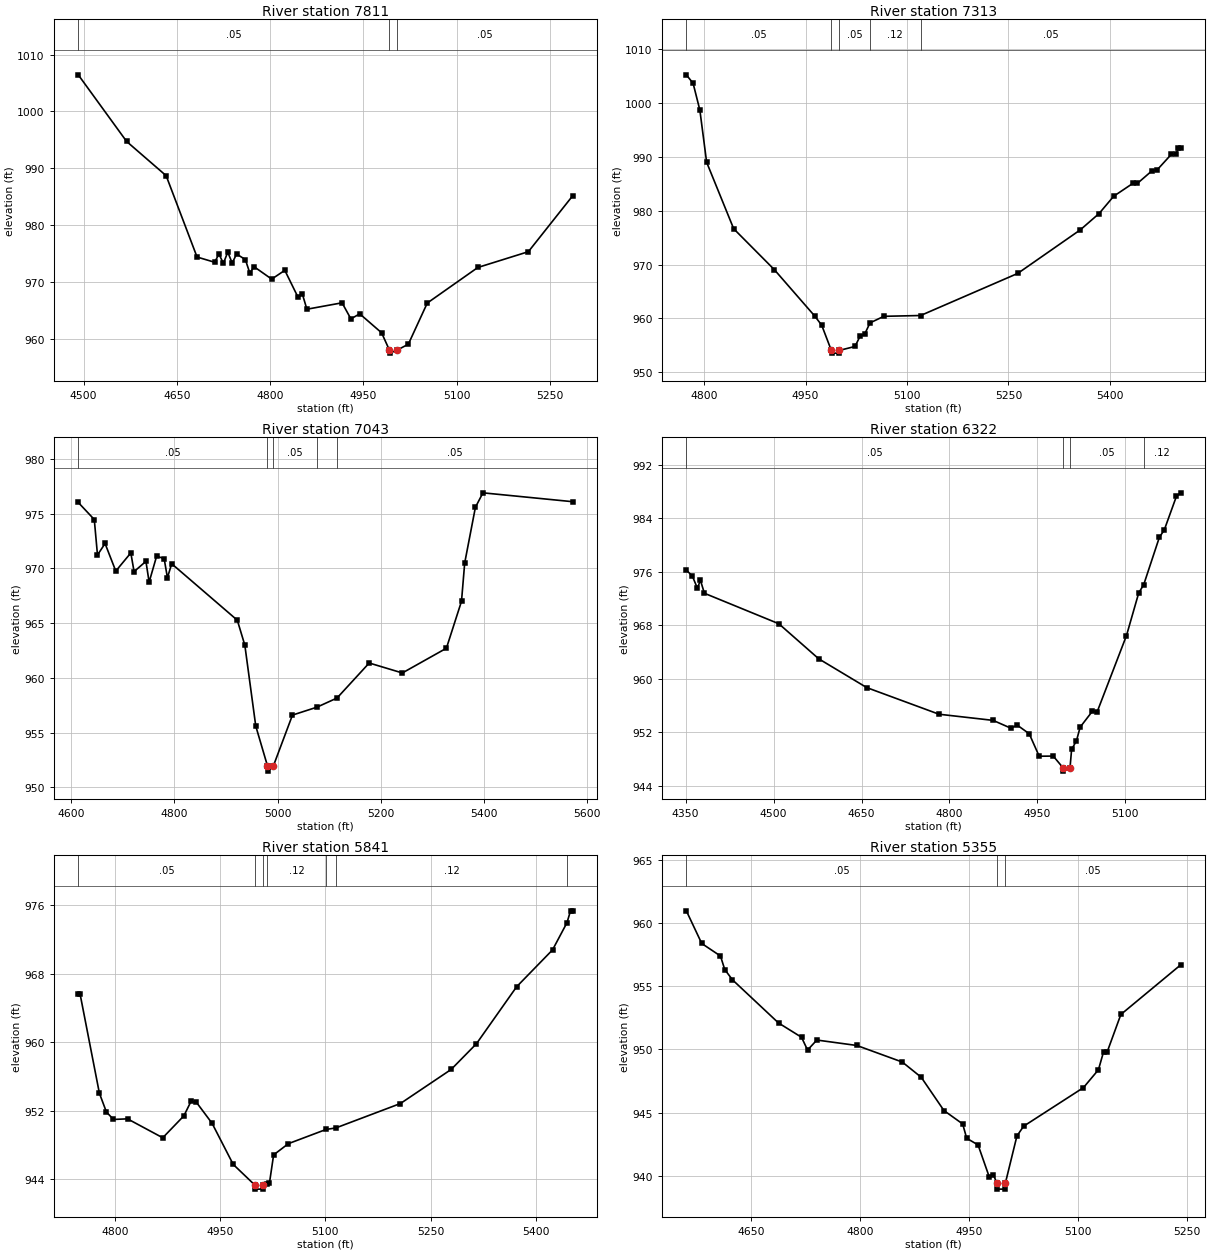
Type RM Length L Ch R = 1 ,7811    ,498,498,498
BEGIN DESCRIPTION:
BEDFORD CREEK 16.0
END DESCRIPTION:
XS GIS Cut Line= 3
      2862305.68     10203903.11       2862673.5       10203552.
      2862955.71     10203603.12
#Sta/Elev= 30
  4491.5 1006.45  4569.3  994.72  4632.9  988.69  4682.6  974.37  4710.9  973.45
  4717.8  974.89    4725  973.26    4732  975.23  4739.2   973.3  4746.1   974.9
  4760.3  973.93  4767.5  971.55  4774.4  972.66  4802.7  970.48  4823.8  972.03
  4845.2  967.26  4852.1  967.83  4859.3  965.18  4915.9  966.31  4930.1  963.48
  4944.3  964.37  4979.5  961.03  4992.2  957.95  4992.7  957.45  5003.9  957.95
  5022.5  959.02    5053  966.27  5134.3  972.53  5215.6  975.31  5286.8  985.14
#Mann= 3 ,-1 , 0
  4491.5     .05       0  4992.2     .03       0  5003.9     .05       0
Bank Sta=4992.2,5003.9
XS Rating Curve= 0 ,0
Exp/Cntr=0.3,0.1

Type RM Length L Ch R = 1 ,7313    ,270,270,270
BEGIN DESCRIPTION:
BEDFORD CREEK 15.0
END DESCRIPTION:
XS GIS Cut Line= 3
      2862505.72     10204053.11      2862731.75       10204042.
      2863105.72     10203703.08
#Sta/Elev= 30
  4773.7  1005.2  4783.7 1003.63  4793.7  998.65  4803.7  988.98  4843.7  976.64
  4903.8  969.05  4963.9  960.39  4973.9  958.73  4988.1  954.06  4988.6  953.56
  4999.3  953.56  4999.8  954.06  5023.1   954.8  5030.6   956.7  5037.3  957.06
  5045.3  959.17  5065.7  960.39  5120.1  960.54  5263.7  968.35  5356.2  976.43
    5384  979.46  5405.6  982.67    5434  985.06  5440.8  985.07  5462.4  987.41
  5469.2  987.47  5490.8  990.44  5497.6  990.51  5501.3   991.6  5504.7   991.6
#Mann= 5 ,-1 , 0
  4773.7     .05       0  4988.1     .05       0  4999.8     .05       0
  5045.3     .12       0  5120.1     .05       0
Bank Sta=4988.1,4999.8
XS Rating Curve= 0 ,0
Exp/Cntr=0.3,0.1

Type RM Length L Ch R = 1 ,7043    ,721,721,721
BEGIN DESCRIPTION:
Mapping XS fef81393
END DESCRIPTION:
XS GIS Cut Line= 4
      2862529.58     10204529.53      2862798.67     10204329.89
      2862989.65     10204112.87      2863258.73     10203913.23
#Sta/Elev= 30
  4613.3  976.03  4644.4  974.47  4650.6  971.23  4665.3  972.28  4686.1  969.76
  4715.3  971.42  4721.6  969.71  4744.6  970.65  4750.8  968.75  4765.4  971.13
    4780  970.89  4786.3  969.15  4794.6  970.43  4921.9  965.27  4936.5  962.99
  4957.7   955.6  4980.3  951.98  4980.8  951.48  4992.1  951.98  5028.9   956.6
  5076.2  957.32  5115.4  958.16  5177.8  961.36  5242.1  960.45  5327.6  962.71
  5356.9     967  5363.1   970.5  5383.9  975.59  5398.5  976.91  5572.5   976.1
#Mann= 5 ,-1 , 0
  4613.3     .05       0  4980.3     .05       0  4992.1     .05       0
  5076.2     .12       0  5115.4     .05       0
Bank Sta=4980.3,4992.1
XS Rating Curve= 0 ,0
Exp/Cntr=0.3,0.1

Type RM Length L Ch R = 1 ,6322    ,481,481,481
BEGIN DESCRIPTION:
BEDFORD CREEK 13.0
END DESCRIPTION:
XS GIS Cut Line= 3
      2862705.64     10204703.12        2863338.       10204558.
      2863455.67     10204403.13
#Sta/Elev= 30
  4351.2  976.26  4361.5  975.35  4370.1  973.54  4375.2  974.75    4382  972.79
    4509  968.23    4577  962.99    4659  958.68  4782.2   954.7  4874.5  953.78
  4905.1   952.6  4915.5  953.08  4936.1  951.78  4953.1  948.42  4977.1  948.44
  4993.8  946.69  4994.3  946.19  5005.7  946.69  5008.4  949.43  5016.7  950.73
    5023  952.77  5043.8  955.14  5052.1  955.08    5102  966.46  5122.8  972.81
  5131.5   974.1  5158.2  981.18  5166.4  982.24  5187.3  987.31  5194.5  987.81
#Mann= 4 ,-1 , 0
  4351.2     .05       0  4993.8     .05       0  5005.7     .05       0
  5131.5     .12       0
Bank Sta=4993.8,5005.7
XS Rating Curve= 0 ,0
Exp/Cntr=0.3,0.1

Type RM Length L Ch R = 1 ,5841    ,486,486,486
BEGIN DESCRIPTION:
BEDFORD CREEK 12.0
END DESCRIPTION:
XS GIS Cut Line= 3
      2863155.72     10205053.11      2863406.75       10205031.
      2863655.68     10204653.12
#Sta/Elev= 30
    4748  965.67  4750.5  965.67  4778.1  954.05  4788.1  951.85  4798.2  950.98
  4818.2  951.05  4868.4  948.84  4898.5   951.4  4908.6  953.08  4916.3  952.99
  4938.7  950.53  4968.8  945.73  4999.3  943.34  4999.8  942.84  5010.8  942.84
  5011.3  943.34  5017.1  943.45  5020.4  943.51  5026.4  946.84  5047.4  948.15
  5101.1  949.81  5115.1  949.99  5207.1  952.84  5279.4  956.82  5315.5  959.83
  5372.7  966.48  5423.9  970.79  5444.5  973.97  5449.5  975.35  5452.5  975.35
#Mann= 7 ,-1 , 0
    4748     .05       0  4999.3     .03       0  5011.3     .05       0
  5017.1     .12       0  5101.1     .05       0  5115.1     .12       0
  5444.5     .05       0
Bank Sta=4999.3,5011.3
XS Rating Curve= 0 ,0
Exp/Cntr=0.3,0.1

Type RM Length L Ch R = 1 ,5355    ,496,496,496
BEGIN DESCRIPTION:
BEDFORD CREEK 11.0
END DESCRIPTION:
XS GIS Cut Line= 3
      2863205.64     10205603.13        2863621.       10205461.
      2863855.67     10205403.12
#Sta/Elev= 30
    4561  960.95  4582.2  958.37    4608  957.38  4613.9  956.31  4624.5   955.5
  4687.9  952.09  4719.6  950.96  4727.9  949.95  4740.7  950.74  4795.8  950.31
  4858.4     949  4884.4   947.8  4915.7  945.17  4941.5  944.11    4947  942.98
  4962.7  942.45  4978.3  939.89  4983.8  940.11  4988.3  939.46  4988.8  938.96
  4999.9  938.96  5000.4  939.46  5016.2  943.16  5025.4  943.93  5107.8  946.98
  5128.4  948.39  5135.5  949.81  5140.6  949.82  5159.3  952.76  5241.7  956.68
#Mann= 3 ,-1 , 0
    4561     .05       0  4988.3     .05       0  5000.4     .05       0
Bank Sta=4988.3,5000.4
XS Rating Curve= 0 ,0
Exp/Cntr=0.3,0.1

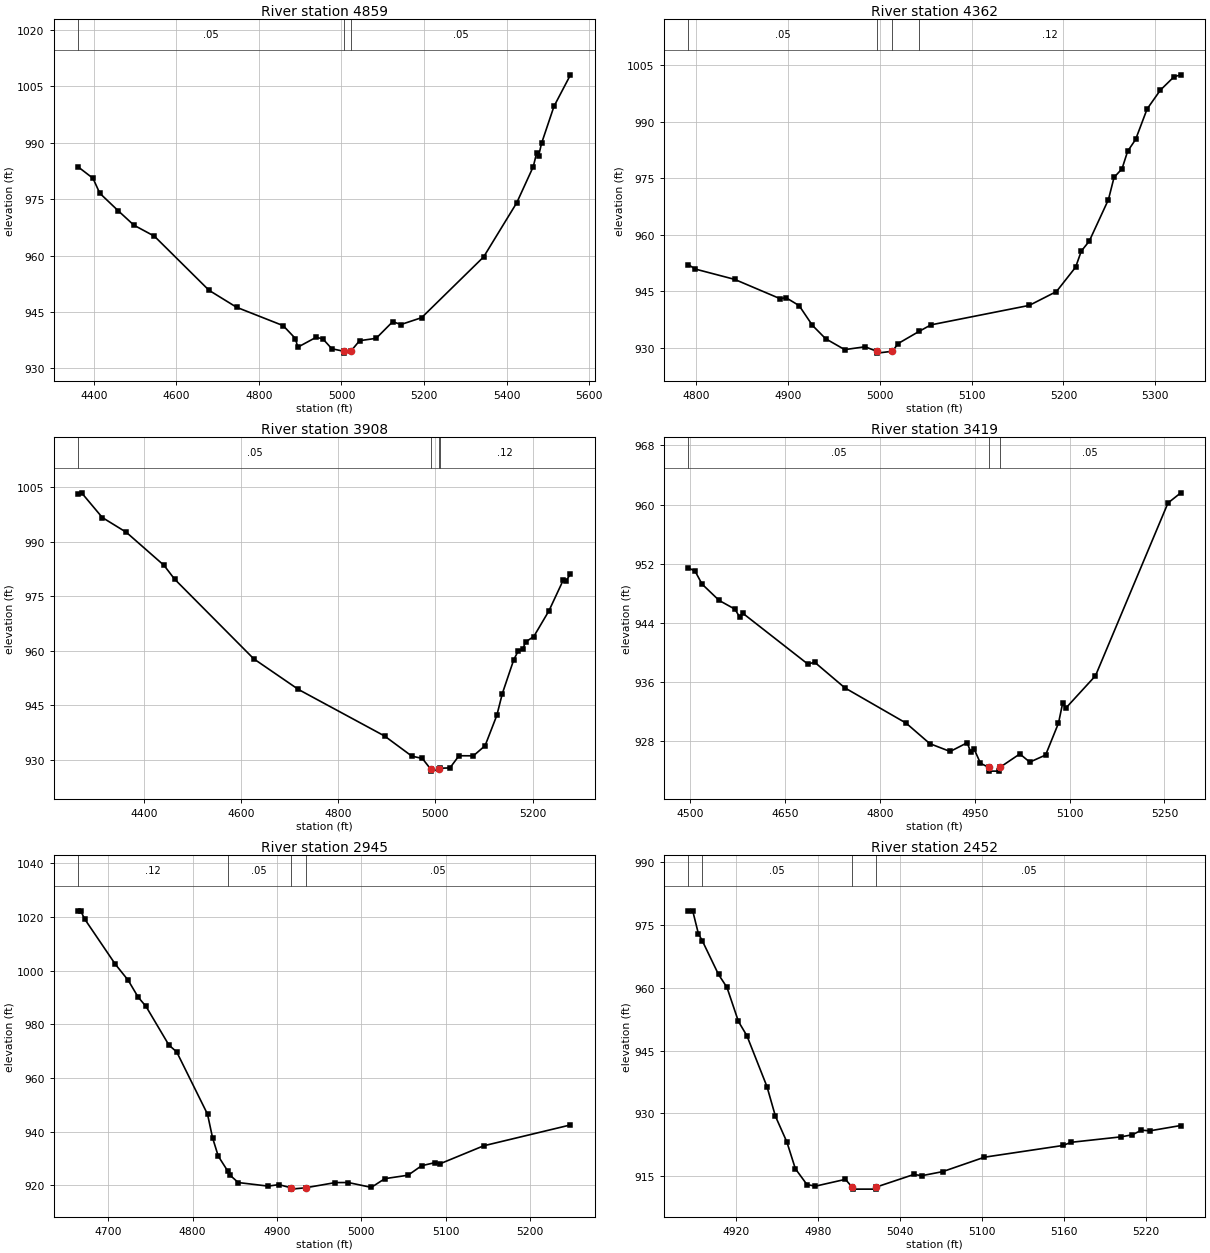
Type RM Length L Ch R = 1 ,4859    ,497,497,497
BEGIN DESCRIPTION:
BEDFORD CREEK 10.0
END DESCRIPTION:
XS GIS Cut Line= 3
      2863555.67     10206453.14      2863851.75       10205888.
      2864405.65     10205853.11
#Sta/Elev= 30
    4362  983.53  4397.9  980.51  4414.4  976.54  4458.5  971.94    4497  968.06
  4546.7  965.13  4679.1  950.76  4745.9  946.25  4858.8  941.37  4888.5  937.94
  4894.1  935.64  4938.2  938.25  4954.7  937.89  4976.7  935.23  5005.4  934.57
  5005.9  934.07  5022.6  934.57    5044  937.37  5084.1     938  5124.2  942.42
  5144.2  941.67  5194.3  943.49  5344.6  959.63  5424.8  974.01  5464.9  983.62
  5472.7  987.12  5477.7  986.42  5484.9  989.79    5515  999.61    5555 1007.99
#Mann= 3 ,-1 , 0
    4362     .05       0  5005.4     .03       0  5022.6     .05       0
Bank Sta=5005.4,5022.6
XS Rating Curve= 0 ,0
Exp/Cntr=0.3,0.1

Type RM Length L Ch R = 1 ,4362    ,454,454,454
BEGIN DESCRIPTION:
BEDFORD CREEK 9.0
END DESCRIPTION:
XS GIS Cut Line= 3
       2864055.7     10206403.09      2864187.75       10206242.
      2864455.67     10206053.12
#Sta/Elev= 30
  4791.7  952.02  4798.9  950.87  4841.9  948.12  4891.4  942.99  4897.9  943.25
  4912.2  941.14  4926.6  935.91    4941  932.35  4961.8  929.44    4984   930.2
  4996.6  929.01  4997.1  928.51  5013.8  929.01    5020  931.06  5043.1  934.33
  5055.7  936.02  5162.8   941.2  5192.4  944.88  5213.3  951.37  5219.4  955.62
  5228.1  958.27    5249  969.33  5255.1  975.22  5263.8  977.52  5269.9  982.17
  5278.6  985.31  5291.1  993.41  5305.6  998.44  5320.4 1001.97  5327.8 1002.49
#Mann= 4 ,-1 , 0
  4791.7     .05       0  4996.6     .05       0  5013.8     .05       0
  5043.1     .12       0
Bank Sta=4996.6,5013.8
XS Rating Curve= 0 ,0
Exp/Cntr=0.3,0.1

Type RM Length L Ch R = 1 ,3908    ,489,489,489
BEGIN DESCRIPTION:
BEDFORD CREEK 8.0
END DESCRIPTION:
XS GIS Cut Line= 3
      2864005.69     10207003.11       2864551.5       10206511.
      2864655.67     10206253.15
#Sta/Elev= 30
  4265.1 1003.33  4272.2 1003.52  4314.8  996.71  4364.1  992.65  4441.8  983.52
  4463.5  979.73  4626.4  957.76  4718.4  949.31  4895.5  936.49  4951.8  930.92
  4973.2  930.31  4990.8   927.3  4991.3   926.8  5008.1   927.3  5009.9   927.6
  5030.1  927.69  5048.7  931.04  5078.3  931.02  5102.4  933.81  5126.5  942.15
  5137.9  948.19  5161.4  957.51  5170.3  959.85  5180.2  960.49  5185.6   962.4
  5202.6   963.9  5233.8     971  5263.4  979.51  5268.8  979.24  5278.1  981.13
#Mann= 4 ,-1 , 0
  4265.1     .05       0  4990.8     .03       0  5008.1     .05       0
  5009.9     .12       0
Bank Sta=4990.8,5008.1
XS Rating Curve= 0 ,0
Exp/Cntr=0.3,0.1

Type RM Length L Ch R = 1 ,3419    ,474,474,474
BEGIN DESCRIPTION:
BEDFORD CREEK 7.0
END DESCRIPTION:
XS GIS Cut Line= 3
      2864855.67     10207153.15      2865007.75       10206674.
      2864955.69     10206403.16
#Sta/Elev= 30
  4497.3  951.43  4507.8  950.98  4518.7  949.24  4545.7  947.03  4570.8  945.84
    4578  944.81  4583.2  945.29  4686.2   938.4  4696.7  938.67  4744.6  935.19
  4841.4  930.42  4878.9  927.64  4911.1  926.58    4938  927.76  4943.4  926.54
  4948.7  926.96    4959  924.99  4972.2  924.42  4972.7  923.92  4989.1  923.92
  4989.6  924.42  5021.3  926.25    5037  925.14    5062   926.1  5082.4  930.42
  5088.9  933.08    5094  932.45  5140.9  936.83  5255.5  960.21  5275.8  961.59
#Mann= 3 ,-1 , 0
  4497.3     .05       0  4972.2     .05       0  4989.6     .05       0
Bank Sta=4972.2,4989.6
XS Rating Curve= 0 ,0
Exp/Cntr=0.3,0.1

Type RM Length L Ch R = 1 ,2945    ,493,493,493
BEGIN DESCRIPTION:
BEDFORD CREEK 6.0
END DESCRIPTION:
XS GIS Cut Line= 3
      2865655.69     10207003.12       2865475.5       10206720.
      2865355.68      10206503.1
#Sta/Elev= 30
  4664.4 1022.25  4667.4 1022.25    4672 1019.25  4708.4 1002.38  4723.7  996.38
  4735.5  990.11  4744.8  986.66  4771.9  972.29  4781.2   969.7  4817.7  946.53
  4823.6  937.83  4830.4  930.92  4841.4  925.49  4844.7  923.73  4854.1  921.08
  4889.6  919.75  4902.3  920.31  4916.4  919.13  4916.9  918.63  4933.9  919.13
  4969.2  921.07  4984.4  921.09  5011.8  919.28  5027.8  922.53  5055.3  923.81
  5071.4  927.34  5087.4  928.51  5093.1  928.05    5145  934.77  5247.8  942.53
#Mann= 4 ,-1 , 0
  4664.4     .12       0  4841.4     .05       0  4916.4     .03       0
  4933.9     .05       0
Bank Sta=4916.4,4933.9
XS Rating Curve= 0 ,0
Exp/Cntr=0.3,0.1

Type RM Length L Ch R = 1 ,2452    ,477,477,477
BEGIN DESCRIPTION:
BEDFORD CREEK 5.0
END DESCRIPTION:
XS GIS Cut Line= 3
      2866005.67      10206603.1        2865913.       10206535.
      2865705.69     10206403.12
#Sta/Elev= 30
    4885  978.41  4888.1  978.41  4892.3  972.89  4895.1  971.27    4907   963.2
  4913.2   960.1  4921.6  951.96  4927.8  948.55  4942.5   936.4  4948.7  929.31
  4957.1  923.14  4963.3  916.76  4971.8  912.97    4978  912.59    5000  914.22
  5004.8  912.38  5005.3  911.88  5022.1  911.88  5022.6  912.38  5050.1  915.38
  5056.1   915.1  5071.3  916.07  5101.8  919.51  5159.3  922.31  5165.3  923.07
  5201.7  924.37  5210.2  924.87  5216.9  925.98  5222.9  925.81  5245.7  927.09
#Mann= 4 ,-1 , 0
    4885     .12       0  4895.1     .05       0  5004.8     .05       0
  5022.6     .05       0
Bank Sta=5004.8,5022.6
XS Rating Curve= 0 ,0
Exp/Cntr=0.3,0.1

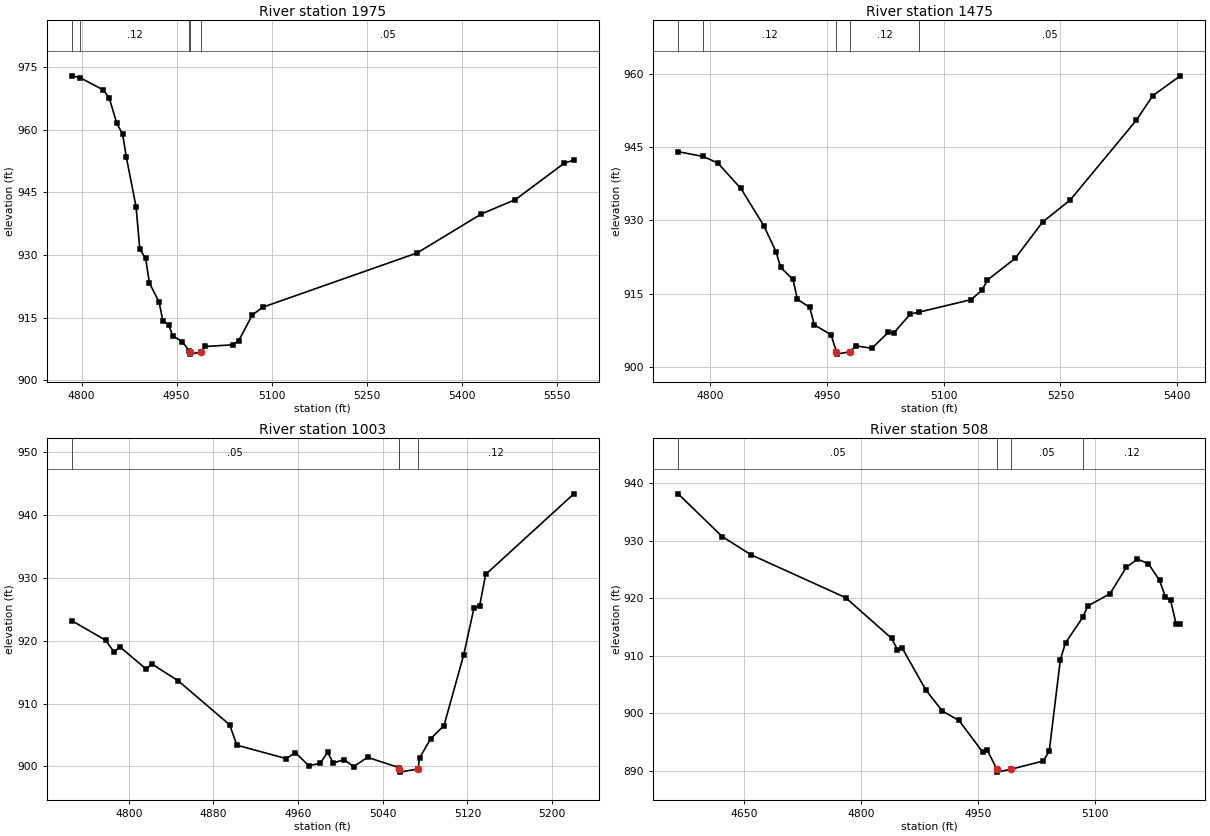
Type RM Length L Ch R = 1 ,1975    ,500,500,500
BEGIN DESCRIPTION:
BEDFORD CREEK 4.0
END DESCRIPTION:
XS GIS Cut Line= 3
      2866255.68      10206303.1      2866140.25       10206121.
      2865605.65      10205903.1
#Sta/Elev= 30
  4784.4   972.9  4797.4  972.48  4834.4  969.52  4843.6  967.67  4855.6  961.54
  4864.9  958.93  4870.8  953.39  4886.1  941.54    4892  931.37  4901.3  929.17
  4907.2  923.28  4922.5  918.73  4928.4  914.22  4937.8  913.28  4943.7  910.66
  4958.9  909.29  4969.9  907.09  4971.2  906.77  4971.7  906.27    4989  906.77
  4995.4   908.1  5038.4  908.49  5048.1  909.48  5069.7  915.67  5086.5  917.52
  5329.9   930.5  5431.5  939.84    5485  943.26  5562.5  952.02  5577.3  952.71
#Mann= 5 ,-1 , 0
  4784.4     .05       0  4797.4     .12       0  4969.9     .05       0
  4971.2     .05       0    4989     .05       0
Bank Sta=4971.2,4989
XS Rating Curve= 0 ,0
Exp/Cntr=0.3,0.1

Type RM Length L Ch R = 1 ,1475    ,472,472,472
BEGIN DESCRIPTION:
BEDFORD CREEK 3.0
END DESCRIPTION:
XS GIS Cut Line= 3
      2866405.66     10205853.08        2866286.       10205644.
      2866005.66     10205353.09
#Sta/Elev= 30
  4759.1  944.08  4791.4  943.09  4810.1  941.75  4839.7  936.54  4869.2  928.91
    4885  923.52  4890.7  920.39  4906.6  917.91  4912.3  913.85  4928.2  912.18
  4933.9  908.62  4955.5  906.59  4962.4  903.12  4962.9  902.62  4980.3  903.12
  4987.2  904.31  5007.9  903.82    5029  907.07  5036.2  906.98  5057.3  910.83
  5068.4  911.22  5135.3  913.77  5149.4  915.73  5156.4   917.8  5191.9  922.22
  5227.1  929.66  5262.6  934.18  5347.5  950.51  5368.6  955.54    5404  959.61
#Mann= 5 ,-1 , 0
  4759.1     .05       0  4791.4     .12       0  4962.4     .07       0
  4980.3     .12       0  5068.4     .05       0
Bank Sta=4962.4,4980.3
XS Rating Curve= 0 ,0
Exp/Cntr=0.3,0.1

Type RM Length L Ch R = 1 ,1003    ,495,495,495
BEGIN DESCRIPTION:
BEDFORD CREEK 2.0
END DESCRIPTION:
XS GIS Cut Line= 3
       2866505.7     10205553.07      2866594.25       10205315.
      2866655.68     10205103.13
#Sta/Elev= 30
    4746  923.22    4778   920.1  4786.1  918.22  4791.5  919.05  4816.5  915.49
  4821.8  916.32  4846.8  913.62  4895.3  906.63  4902.2  903.38  4948.7  901.25
  4957.5  902.19    4970  900.13  4980.7  900.47  4987.9  902.24  4993.2  900.55
  5003.6  901.09  5012.4  899.96  5025.6  901.45  5055.1  899.82  5055.4  899.59
  5055.9  899.09  5073.4  899.59  5074.8  901.35  5085.3  904.41  5097.9  906.51
  5116.5  917.76  5126.3  925.28  5131.5  925.52  5137.3  930.58  5220.6  943.41
#Mann= 4 ,-1 , 0
    4746     .05       0  5055.1     .12       0  5055.4     .05       0
  5073.4     .12       0
Bank Sta=5055.4,5073.4
XS Rating Curve= 0 ,0
Exp/Cntr=0.3,0.1

Type RM Length L Ch R = 1 ,508     ,0,0,0
BEGIN DESCRIPTION:
BEDFORD CREEK 1.0
END DESCRIPTION:
XS GIS Cut Line= 3
      2866513.99     10205848.96      2866881.75       10205617.
      2867039.04     10205479.07
#Sta/Elev= 30
  4565.2  938.15  4621.7  930.73  4658.2  927.59    4780   920.1  4839.1  913.02
  4846.5  911.04  4852.4  911.38    4883  904.02  4904.2  900.37  4925.4  898.75
  4955.9  893.23  4961.8  893.55    4974  890.27  4974.5  889.77    4992  890.27
  5033.6  891.71  5041.1  893.42  5055.4  909.34    5062  912.24  5084.4  916.73
  5090.5  918.65    5119  920.78  5139.9  925.35  5154.1  926.81  5168.3     926
  5182.6  923.11  5190.1  920.19  5196.8  919.64  5203.7  915.56  5209.2  915.56
#Mann= 4 ,-1 , 0
  4565.2     .05       0    4974     .05       0    4992     .05       0
  5084.4     .12       0
Bank Sta=4974,4992
XS Rating Curve= 0 ,0
Exp/Cntr=0.3,0.1

Chan Stop Cuts=-1
Use User Specified Reach Order=0
Composite Channel Slope=5