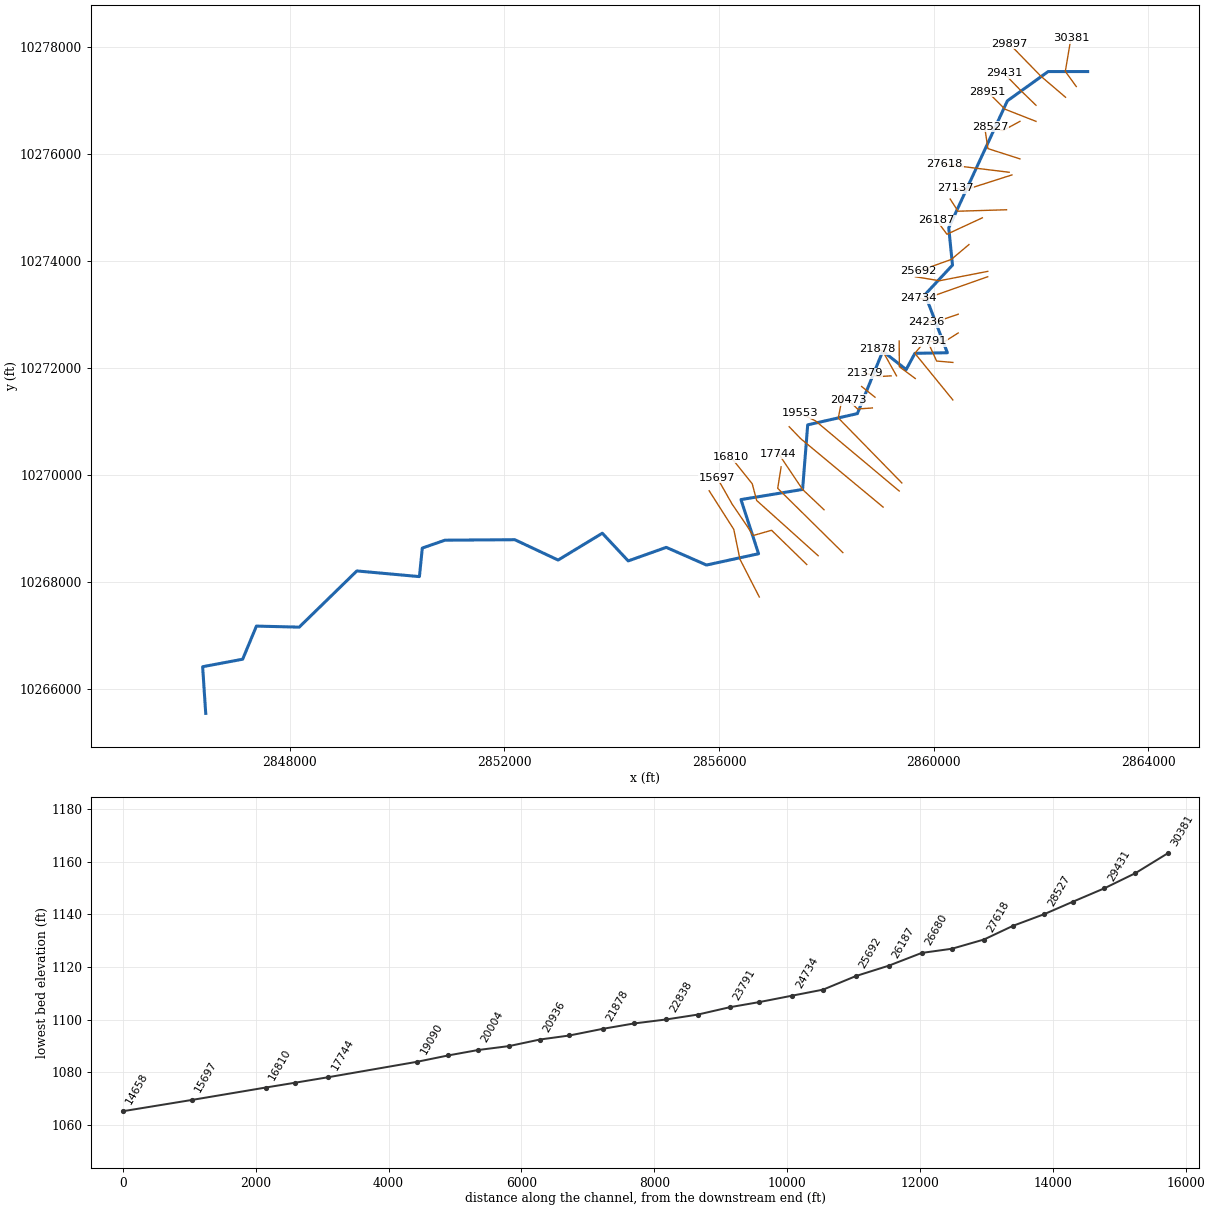
--- BOARD BRANCH.prj (project) ---

Proj Title=BOARD BRANCH Base Level Engineering
Current Plan=p01
Default Exp/Contr=0.3,0.1
English Units
Geom File=g01
Flow File=f01
Plan File=p01
BEGIN DESCRIPTION:
BOARD BRANCH
END DESCRIPTION:

--- BOARD BRANCH.p01 (plan) ---

Plan Title=Multiple Run
Short Identifier=Multiple
Geom File=g01
Flow File=f01
Subcritical Flow
K Sum by GR= 0
Std Step Tol= 0.01
Critical Tol= 0.01
Num of Std Step Trials= 20
Max Error Tol= 0.3
Flow Tol Ratio= 0.001
Split Flow NTrial= 30
Split Flow Tol= 0.02
Split Flow Ratio= 0.02
Log Output Level= 0
Friction Slope Method= 1
Unsteady Friction Slope Method= 2
Unsteady Bridges Friction Slope Method= 1
Parabolic Critical Depth
Global Vel Dist=  1 , 1 , 1
Global Log Level= 0
CheckData=True
Encroach Param= -1, 0, 0, 0
BEGIN DESCRIPTION:
Multiple Run
END DESCRIPTION:

--- BOARD BRANCH.f01 (steady flow) ---

Flow Title=Multiple
Number of Profiles=7
Profile Names=10-year,25-year,50-year,1pct_min,100-year,1pct_plu,500-year
River Rch & RM= BOARD BRANCH,Reach-1,30381
     468     763    1387    1059    1929    3513    2773
River Rch & RM= BOARD BRANCH,Reach-1,20004
     895    1532    2443    1688    3420    6932    4834
River Rch & RM= BOARD BRANCH,Reach-1,9299
     922    1583    2499    1715    3498    7135    4940
River Rch & RM= BOARD BRANCH,Reach-1,8367
    1290    2255    3735    2578    5292   10863    7432
River Rch & RM= BOARD BRANCH,Reach-1,4249
    1517    2679    4514    3094    6435   13385    9033
River Rch & RM= BOARD BRANCH,Reach-1,968
    1619    2868    4912    3376    7023   14611    9856
Boundary for River Rch & Prof#=BOARD BRANCH,Reach-1,1
Up Type=0
Dn Type=3
Dn Slope=0.005
Boundary for River Rch & Prof#=BOARD BRANCH,Reach-1,2
Up Type=0
Dn Type=3
Dn Slope=0.005
Boundary for River Rch & Prof#=BOARD BRANCH,Reach-1,3
Up Type=0
Dn Type=3
Dn Slope=0.005
Boundary for River Rch & Prof#=BOARD BRANCH,Reach-1,4
Up Type=0
Dn Type=3
Dn Slope=0.005
Boundary for River Rch & Prof#=BOARD BRANCH,Reach-1,5
Up Type=0
Dn Type=3
Dn Slope=0.005
Boundary for River Rch & Prof#=BOARD BRANCH,Reach-1,6
Up Type=0
Dn Type=3
Dn Slope=0.005
Boundary for River Rch & Prof#=BOARD BRANCH,Reach-1,7
Up Type=0
Dn Type=3
Dn Slope=0.005

--- BOARD BRANCH.g01 (geometry) ---

Geom Title=Existing Conditions

River Reach=BOARD BRANCH,Reach-1
Reach XY= 30
      2862868.00     10277533.00      2862131.75     10277533.00
      2861371.50     10276986.00      2860279.00     10274616.00
      2860349.00     10273920.00      2859837.75     10273370.00
      2860253.50     10272284.00      2859648.25     10272273.00
      2859485.75     10271970.00      2859049.50     10272313.00
      2858576.50     10271148.00      2857651.00     10270938.00
      2857555.50     10269732.00      2856407.25     10269543.00
      2856735.25     10268532.00      2855765.25     10268321.00
      2855015.25     10268651.00      2854306.50     10268398.00
      2853823.75     10268915.00      2853000.25     10268414.00
      2852192.75     10268794.00      2850891.75     10268785.00
      2850469.50     10268638.00      2850415.50     10268105.00
      2849249.50     10268211.00      2848176.00     10267162.00
      2847378.25     10267181.00      2847121.75     10266563.00
      2846376.00     10266423.00      2846433.50     10265552.00

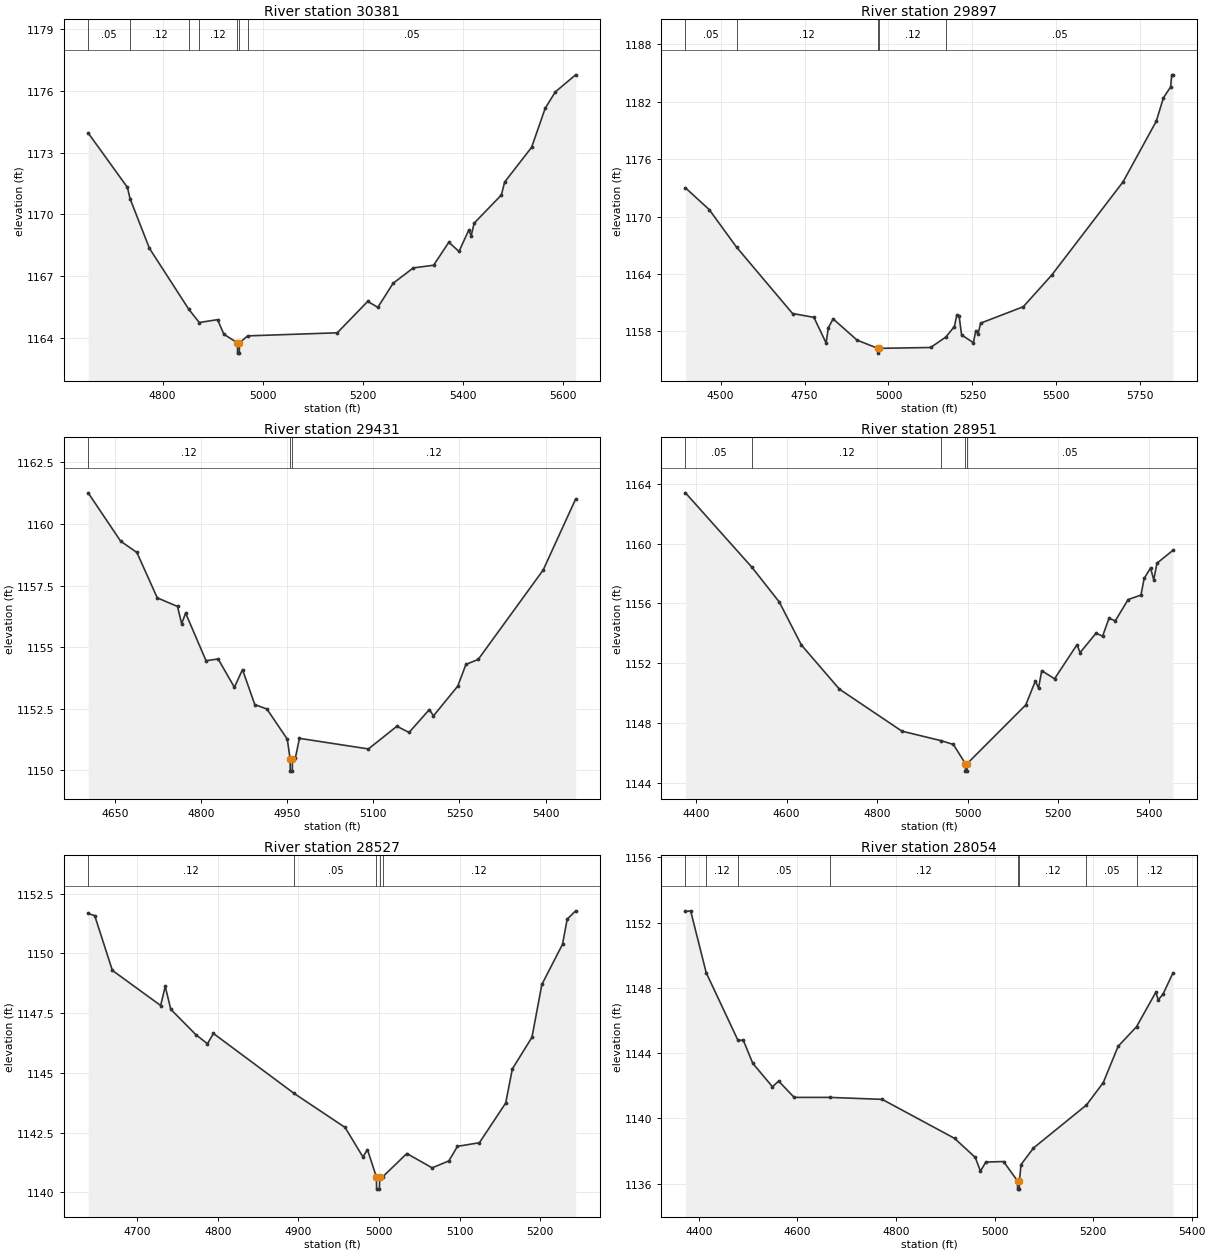
Type RM Length L Ch R = 1,30381,484,484,484
BEGIN DESCRIPTION:
BOARD BRANCH 58.0
END DESCRIPTION:
XS GIS Cut Line= 3
      2862655.67     10277253.13      2862451.25     10277536.00
      2862555.69     10278153.13
#Sta/Elev= 30
  4651.0 1173.96  4729.5 1171.31  4734.8 1170.76  4773.6 1168.34  4852.4 1165.37
  4873.2 1164.73  4909.8 1164.87  4922.4 1164.16  4949.5 1163.74  4949.8 1163.24
  4953.3 1163.24  4953.5 1163.74  4970.0 1164.08  5149.2 1164.23  5210.1 1165.76
  5230.3 1165.47  5260.8 1166.64  5301.3 1167.39  5341.9 1167.52  5372.3 1168.64
  5392.6 1168.19  5412.0 1169.22  5417.0 1168.96  5423.0 1169.57  5477.4 1170.94
  5483.9 1171.57  5537.8 1173.26  5565.0 1175.16  5585.3 1175.96  5625.9 1176.79
#Mann=7,-1,0
  4651.0    0.05       0  4734.8    0.12       0  4852.4    0.05       0
  4873.2    0.12       0  4949.5    0.05       0  4953.5    0.12       0
  4970.0    0.05       0
Bank Sta=4949.5,4953.5
Exp/Cntr=0.3,0.1

Type RM Length L Ch R = 1,29897,466,466,466
BEGIN DESCRIPTION:
BOARD BRANCH 57.0
END DESCRIPTION:
XS GIS Cut Line= 3
      2862455.67     10277053.12      2861996.25     10277446.00
      2861405.66     10278053.14
#Sta/Elev= 30
  4395.5 1173.00  4466.3 1170.72  4547.6 1166.80  4714.4 1159.86  4778.0 1159.46
  4814.3 1156.78  4820.9 1158.37  4835.1 1159.30  4906.5 1157.08  4968.2 1156.22
  4968.4 1155.72  4972.2 1156.22  5125.6 1156.31  5170.8 1157.40  5196.3 1158.50
  5203.5 1159.71  5210.5 1159.56  5217.7 1157.62  5252.9 1156.81  5260.1 1158.08
  5267.1 1157.76  5274.2 1158.85  5401.4 1160.57  5486.2 1163.88  5698.4 1173.62
  5797.5 1179.97  5818.8 1182.42  5839.9 1183.53  5843.5 1184.81  5847.0 1184.81
#Mann=5,-1,0
  4395.5    0.05       0  4547.6    0.12       0  4968.2    0.07       0
  4972.2    0.12       0  5170.8    0.05       0
Bank Sta=4968.2,4972.2
Exp/Cntr=0.3,0.1

Type RM Length L Ch R = 1,29431,480,480,480
BEGIN DESCRIPTION:
BOARD BRANCH 56.0
END DESCRIPTION:
XS GIS Cut Line= 3
      2861905.72     10276903.08      2861621.25     10277179.00
      2861305.66     10277503.14
#Sta/Elev= 30
  4603.7 1161.26  4660.2 1159.30  4688.5 1158.84  4724.0 1157.00  4759.3 1156.65
  4766.4 1155.95  4773.4 1156.38  4808.9 1154.45  4830.0 1154.52  4858.3 1153.37
  4872.4 1154.09  4893.8 1152.67  4914.9 1152.49  4950.3 1151.27  4955.3 1150.47
  4955.6 1149.97  4959.1 1149.97  4959.3 1150.47  4964.5 1150.51  4971.5 1151.30
  5091.6 1150.87  5141.2 1151.79  5162.4 1151.54  5197.8 1152.47  5204.8 1152.21
  5247.2 1153.42  5261.4 1154.30  5282.7 1154.50  5395.9 1158.13  5452.4 1161.01
#Mann=3,-1,0
  4603.7    0.12       0  4955.3    0.07       0  4959.3    0.12       0
Bank Sta=4955.3,4959.3
Exp/Cntr=0.3,0.1

Type RM Length L Ch R = 1,28951,424,424,424
BEGIN DESCRIPTION:
BOARD BRANCH 55.0
END DESCRIPTION:
XS GIS Cut Line= 3
      2861905.65     10276603.12      2861325.50     10276831.00
      2861005.69     10277153.10
#Sta/Elev= 30
  4376.7 1163.39  4523.8 1158.41  4584.0 1156.10  4632.8 1153.23  4716.8 1150.28
  4855.0 1147.47  4942.3 1146.83  4968.8 1146.58  4995.2 1145.30  4995.5 1144.80
  4999.0 1144.80  4999.2 1145.30  5128.7 1149.22  5149.9 1150.82  5156.9 1150.35
  5164.0 1151.51  5192.3 1150.97  5241.8 1153.24  5248.8 1152.72  5284.2 1154.02
  5298.4 1153.81  5312.5 1155.00  5326.7 1154.85  5354.9 1156.26  5383.2 1156.56
  5390.3 1157.67  5404.4 1158.37  5411.5 1157.58  5418.6 1158.69  5453.9 1159.55
#Mann=5,-1,0
  4376.7    0.05       0  4523.8    0.12       0  4942.3    0.05       0
  4995.2    0.05       0  4999.2    0.05       0
Bank Sta=4995.2,4999.2
Exp/Cntr=0.3,0.1

Type RM Length L Ch R = 1,28527,473,473,473
BEGIN DESCRIPTION:
BOARD BRANCH 54.0
END DESCRIPTION:
XS GIS Cut Line= 3
      2861605.73     10276603.13      2861288.75     10276431.00
      2861055.65     10276503.12
#Sta/Elev= 30
  4639.3 1151.67  4647.4 1151.58  4669.3 1149.29  4729.2 1147.82  4734.9 1148.62
  4741.8 1147.66  4772.9 1146.60  4787.3 1146.22  4794.7 1146.65  4894.9 1144.14
  4958.0 1142.72  4980.1 1141.49  4985.8 1141.79  4996.9 1140.64  4997.1 1140.14
  5000.6 1140.14  5000.9 1140.64  5004.5 1140.65  5034.6 1141.63  5066.0 1141.03
  5086.7 1141.32  5097.4 1141.93  5124.6 1142.08  5157.2 1143.74  5165.5 1145.17
  5189.8 1146.49  5202.1 1148.70  5227.7 1150.38  5233.5 1151.43  5244.0 1151.78
#Mann=5,-1,0
  4639.3    0.12       0  4894.9    0.05       0  4996.9    0.05       0
  5000.9    0.05       0  5004.5    0.12       0
Bank Sta=4996.9,5000.9
Exp/Cntr=0.3,0.1

Type RM Length L Ch R = 1,28054,436,436,436
BEGIN DESCRIPTION:
BOARD BRANCH 53.0
END DESCRIPTION:
XS GIS Cut Line= 3
      2861605.73     10275903.10      2861008.50     10276095.00
      2860955.68     10276453.13
#Sta/Elev= 30
  4372.7 1152.68  4383.2 1152.72  4414.8 1148.93  4478.9 1144.81  4490.3 1144.78
  4509.3 1143.38  4549.3 1141.94  4561.8 1142.29  4593.3 1141.29  4665.7 1141.29
  4771.9 1141.17  4918.9 1138.78  4960.9 1137.61  4971.4 1136.77  4982.3 1137.33
  5018.3 1137.36  5046.6 1136.17  5046.8 1135.67  5050.3 1135.67  5050.6 1136.17
  5053.6 1137.17  5079.0 1138.19  5186.4 1140.82  5220.5 1142.19  5250.8 1144.42
  5288.1 1145.62  5327.2 1147.73  5332.2 1147.27  5341.8 1147.61  5362.0 1148.91
#Mann=8,-1,0
  4372.7    0.05       0  4414.8    0.12       0  4478.9    0.05       0
  4665.7    0.12       0  5046.6    0.07       0  5050.6    0.12       0
  5186.4    0.05       0  5288.1    0.12       0
Bank Sta=5046.6,5050.6
Exp/Cntr=0.3,0.1

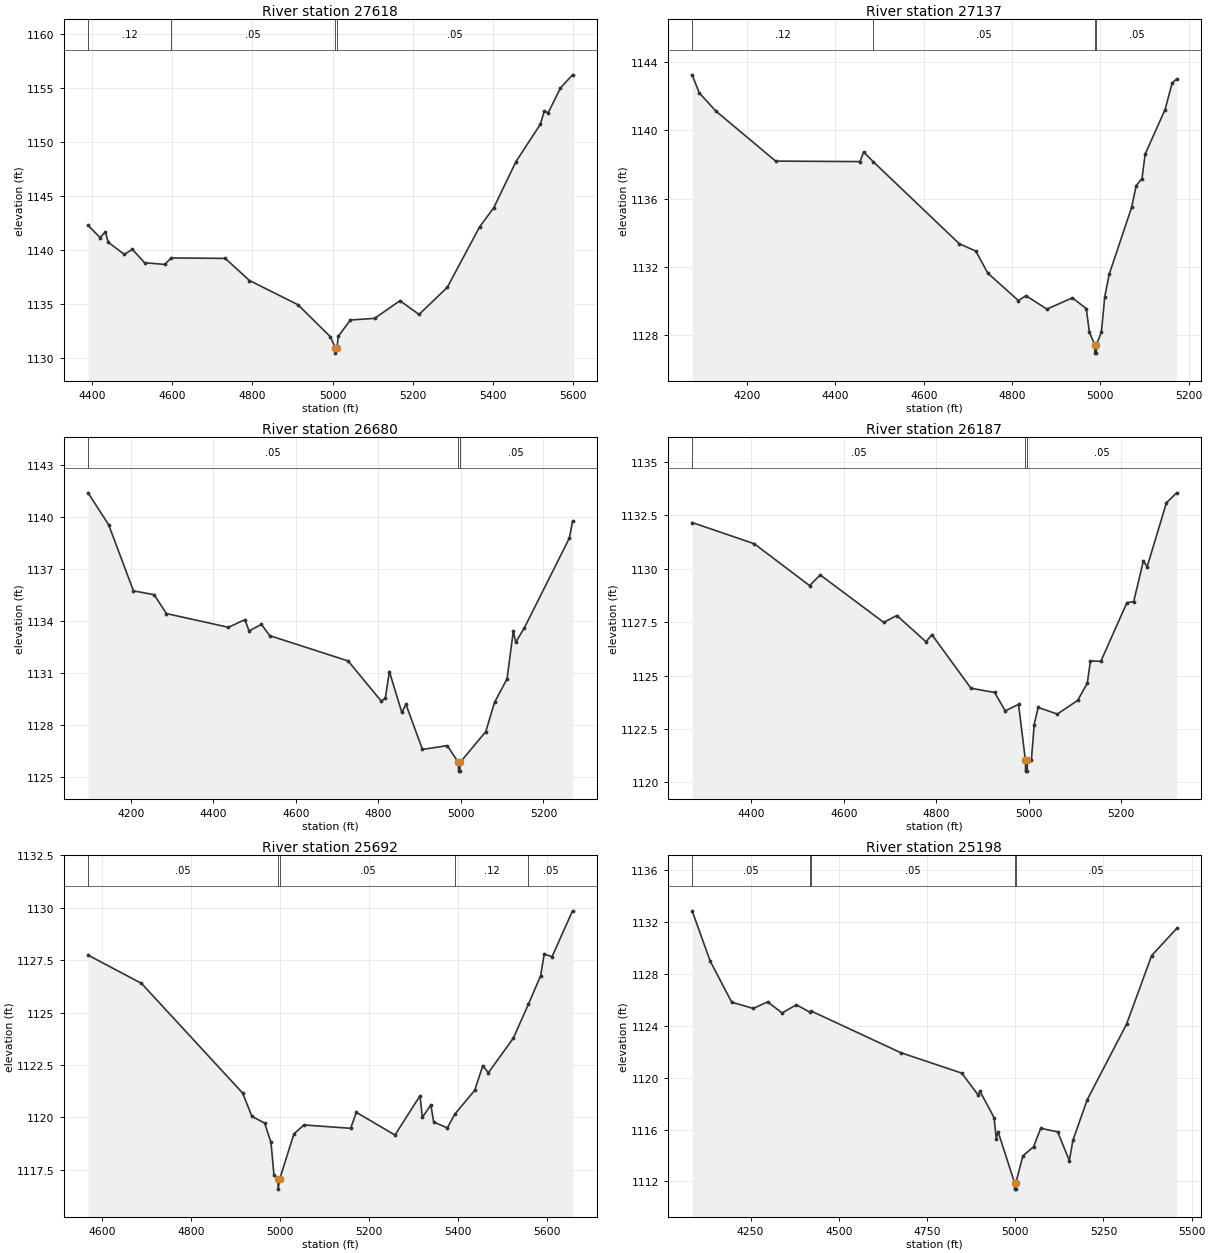
Type RM Length L Ch R = 1,27618,481,481,481
BEGIN DESCRIPTION:
BOARD BRANCH 52.0
END DESCRIPTION:
XS GIS Cut Line= 3
      2861405.66     10275653.11      2860799.75     10275727.00
      2860205.71     10275803.11
#Sta/Elev= 30
  4389.6 1142.32  4419.8 1141.17  4432.9 1141.71  4439.9 1140.75  4480.2 1139.62
  4500.4 1140.09  4530.6 1138.85  4581.0 1138.69  4597.1 1139.29  4732.1 1139.25
  4792.5 1137.20  4913.4 1134.96  4994.0 1132.01  5006.9 1130.97  5007.2 1130.47
  5010.9 1130.97  5014.2 1132.02  5044.4 1133.54  5104.9 1133.69  5168.3 1135.33
  5215.8 1134.05  5286.4 1136.57  5367.0 1142.17  5402.3 1143.94  5457.8 1148.22
  5518.3 1151.66  5528.3 1152.87  5538.4 1152.76  5568.7 1155.04  5598.9 1156.26
#Mann=4,-1,0
  4389.6    0.12       0  4597.1    0.05       0  5006.9    0.05       0
  5010.9    0.05       0
Bank Sta=5006.9,5010.9
Exp/Cntr=0.3,0.1

Type RM Length L Ch R = 1,27137,457,457,457
BEGIN DESCRIPTION:
BOARD BRANCH 51.0
END DESCRIPTION:
XS GIS Cut Line= 3
      2861455.66     10275603.10      2860575.25     10275321.00
      2860405.66     10275353.12
#Sta/Elev= 30
  4075.5 1143.23  4091.5 1142.18  4128.9 1141.12  4264.5 1138.19  4455.5 1138.16
  4464.0 1138.72  4485.7 1138.15  4680.5 1133.36  4717.9 1132.93  4744.8 1131.65
  4814.3 1130.04  4831.5 1130.33  4878.6 1129.54  4936.5 1130.20  4968.0 1129.57
  4975.0 1128.19  4987.0 1127.47  4987.3 1126.97  4990.8 1126.97  4991.0 1127.47
  5002.3 1128.20  5009.7 1130.25  5019.9 1131.58  5070.8 1135.50  5081.0 1136.76
  5094.1 1137.17  5101.3 1138.60  5146.4 1141.20  5162.4 1142.75  5172.6 1142.99
#Mann=4,-1,0
  4075.5    0.12       0  4485.7    0.05       0  4987.0    0.03       0
  4991.0    0.05       0
Bank Sta=4987,4991
Exp/Cntr=0.3,0.1

Type RM Length L Ch R = 1,26680,493,493,493
BEGIN DESCRIPTION:
BOARD BRANCH 50.0
END DESCRIPTION:
XS GIS Cut Line= 3
      2861355.69     10274953.11      2860452.50     10274926.00
      2860305.70     10275153.08
#Sta/Elev= 30
  4096.4 1141.40  4146.4 1139.56  4206.5 1135.75  4256.5 1135.53  4286.5 1134.44
  4436.6 1133.65  4476.6 1134.09  4486.6 1133.44  4516.6 1133.82  4536.6 1133.17
  4726.7 1131.71  4806.7 1129.40  4816.7 1129.55  4826.7 1131.10  4856.8 1128.74
  4866.8 1129.21  4906.8 1126.61  4966.8 1126.83  4993.9 1125.86  4994.2 1125.36
  4997.7 1125.36  4997.9 1125.86  5060.3 1127.64  5081.4 1129.32  5111.8 1130.68
  5126.9 1133.43  5132.9 1132.79  5154.0 1133.63  5262.9 1138.80  5270.4 1139.75
#Mann=3,-1,0
  4096.4    0.05       0  4993.9    0.05       0  4997.9    0.05       0
Bank Sta=4993.9,4997.9
Exp/Cntr=0.3,0.1

Type RM Length L Ch R = 1,26187,495,495,495
BEGIN DESCRIPTION:
BOARD BRANCH 49.0
END DESCRIPTION:
XS GIS Cut Line= 3
      2860905.66     10274803.10      2860245.50     10274496.00
      2860055.68     10274753.12
#Sta/Elev= 30
  4271.9 1132.16  4406.0 1131.17  4525.9 1129.21  4548.8 1129.71  4686.1 1127.49
  4714.5 1127.81  4777.7 1126.58  4790.2 1126.92  4874.7 1124.41  4926.0 1124.21
  4948.9 1123.35  4977.7 1123.65  4992.6 1121.03  4992.9 1120.53  4996.4 1120.53
  4996.6 1121.03  5005.4 1121.03  5011.6 1122.71  5020.0 1123.51  5061.7 1123.20
  5105.6 1123.84  5126.4 1124.65  5133.1 1125.68  5155.7 1125.67  5212.0 1128.41
  5226.7 1128.46  5247.5 1130.35  5255.9 1130.10  5297.6 1133.09  5319.6 1133.55
#Mann=3,-1,0
  4271.9    0.05       0  4992.6    0.05       0  4996.6    0.05       0
Bank Sta=4992.6,4996.6
Exp/Cntr=0.3,0.1

Type RM Length L Ch R = 1,25692,494,494,494
BEGIN DESCRIPTION:
BOARD BRANCH 48.0
END DESCRIPTION:
XS GIS Cut Line= 3
      2860655.69     10274303.12      2860325.25     10274025.00
      2859705.68     10273803.11
#Sta/Elev= 30
  4568.1 1127.74  4688.4 1126.39  4916.0 1121.16  4936.8 1120.05  4965.4 1119.73
  4979.7 1118.81  4986.4 1117.26  4995.6 1117.08  4995.8 1116.58  4999.6 1117.08
  5031.4 1119.22  5054.0 1119.64  5158.9 1119.48  5171.8 1120.24  5258.7 1119.16
  5315.0 1121.03  5320.3 1120.00  5339.4 1120.60  5345.7 1119.78  5376.5 1119.50
  5393.4 1120.16  5438.0 1121.29  5456.3 1122.47  5468.8 1122.13  5525.0 1123.78
  5558.7 1125.39  5586.5 1126.76  5594.4 1127.79  5612.0 1127.66  5658.1 1129.85
#Mann=5,-1,0
  4568.1    0.05       0  4995.6    0.05       0  4999.6    0.05       0
  5393.4    0.12       0  5558.7    0.05       0
Bank Sta=4995.6,4999.6
Exp/Cntr=0.3,0.1

Type RM Length L Ch R = 1,25198,464,464,464
BEGIN DESCRIPTION:
BOARD BRANCH 47.0
END DESCRIPTION:
XS GIS Cut Line= 3
      2861005.70     10273803.11      2860107.00     10273628.00
      2859655.71     10273703.11
#Sta/Elev= 30
  4084.4 1132.88  4135.4 1129.01  4196.5 1125.83  4257.6 1125.35  4298.4 1125.86
  4339.1 1125.00  4379.9 1125.63  4419.0 1125.05  4422.5 1125.14  4675.3 1121.94
  4848.5 1120.36  4894.6 1118.68  4899.7 1118.98  4940.2 1116.92  4946.2 1115.30
  4951.3 1115.85  4998.0 1111.91  4998.2 1111.41  5001.7 1111.41  5002.0 1111.91
  5021.6 1113.97  5052.0 1114.68  5072.3 1116.10  5120.2 1115.83  5153.4 1113.61
  5163.5 1115.18  5204.1 1118.31  5315.6 1124.14  5386.6 1129.43  5457.5 1131.52
#Mann=5,-1,0
  4084.4    0.05       0  4419.0    0.12       0  4422.5    0.05       0
  4998.0    0.05       0  5002.0    0.05       0
Bank Sta=4998,5002
Exp/Cntr=0.3,0.1

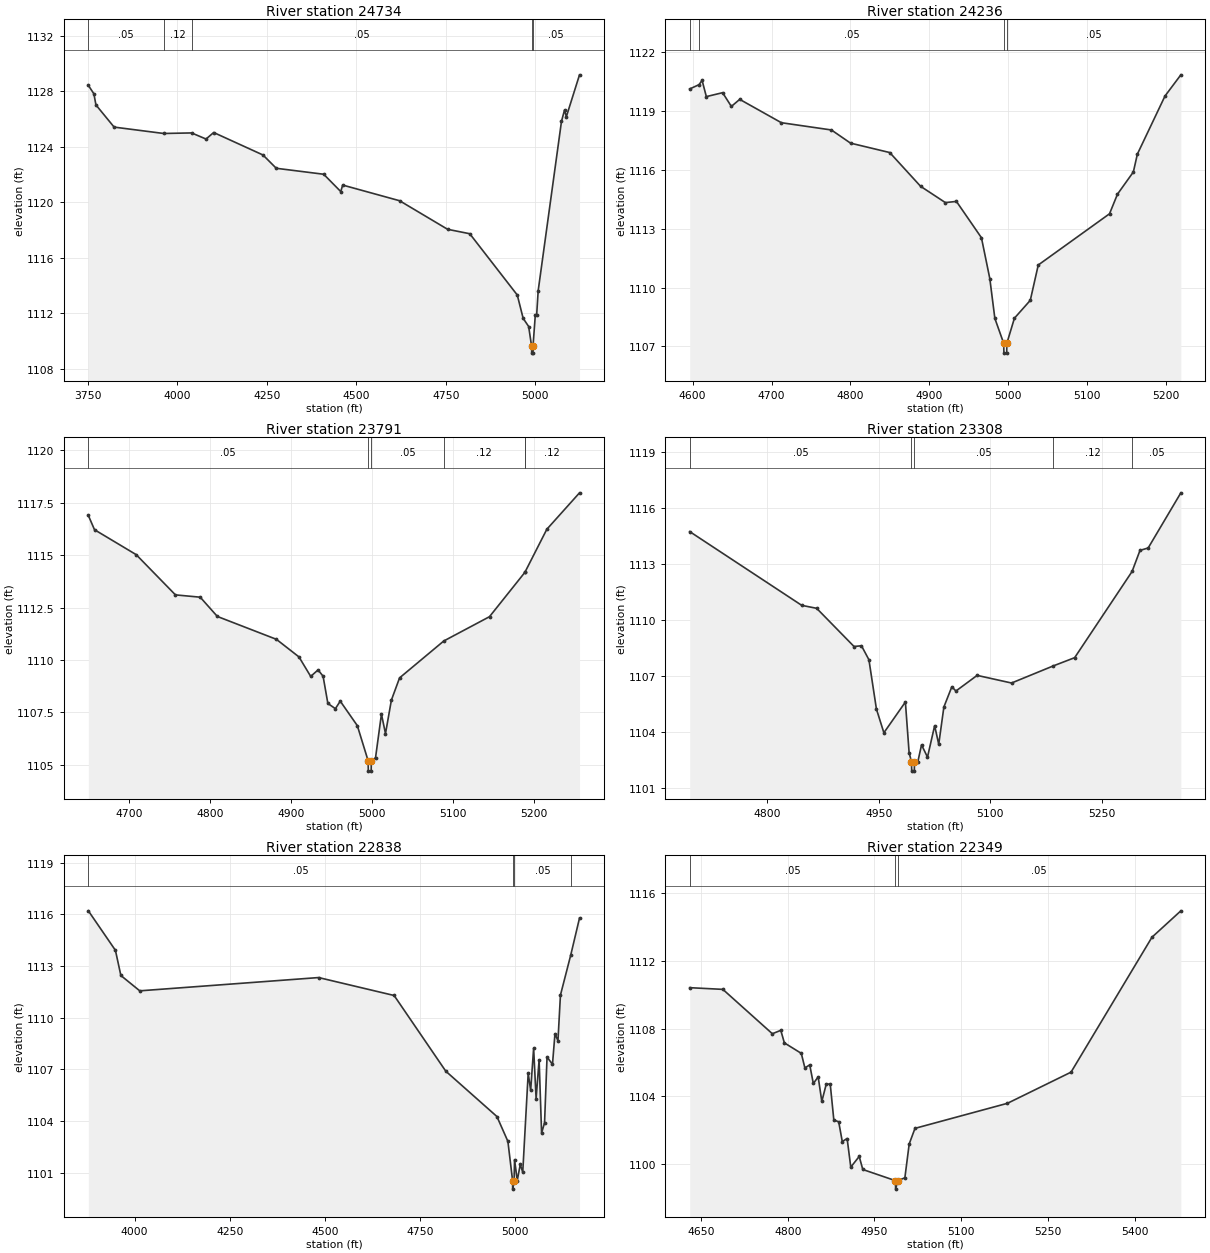
Type RM Length L Ch R = 1,24734,498,498,498
BEGIN DESCRIPTION:
BOARD BRANCH 46.0
END DESCRIPTION:
XS GIS Cut Line= 3
      2861005.68     10273703.11      2859828.25     10273287.00
      2859705.70     10273303.11
#Sta/Elev= 30
  3751.2 1128.43  3766.7 1127.82  3772.4 1127.02  3823.2 1125.42  3961.8 1124.96
  4039.7 1125.00  4080.0 1124.56  4101.4 1125.03  4239.1 1123.41  4276.3 1122.45
  4408.8 1122.02  4456.5 1120.77  4461.8 1121.24  4620.9 1120.11  4755.0 1118.05
  4816.9 1117.73  4949.7 1113.31  4966.1 1111.63  4981.5 1111.04  4989.7 1109.62
  4990.0 1109.12  4993.5 1109.12  4993.7 1109.62  5000.0 1111.85  5003.8 1111.85
  5008.1 1113.62  5073.2 1125.83  5081.7 1126.65  5086.8 1126.17  5123.6 1129.19
#Mann=5,-1,0
  3751.2    0.05       0  3961.8    0.12       0  4039.7    0.05       0
  4989.7    0.03       0  4993.7    0.05       0
Bank Sta=4989.7,4993.7
Exp/Cntr=0.3,0.1

Type RM Length L Ch R = 1,24236,445,445,445
BEGIN DESCRIPTION:
BOARD BRANCH 45.0
END DESCRIPTION:
XS GIS Cut Line= 3
      2860455.66     10273003.10      2860073.50     10272873.00
      2859855.71     10272853.11
#Sta/Elev= 30
  4596.3 1120.12  4608.2 1120.34  4612.0 1120.56  4617.4 1119.73  4638.0 1119.93
  4649.1 1119.23  4659.7 1119.59  4712.5 1118.40  4775.9 1118.03  4800.1 1117.36
  4849.8 1116.88  4888.9 1115.16  4920.3 1114.33  4934.3 1114.39  4966.0 1112.54
  4976.6 1110.46  4983.0 1108.43  4994.2 1107.16  4994.5 1106.66  4998.0 1106.66
  4998.2 1107.16  5007.8 1108.44  5027.9 1109.35  5038.0 1111.15  5128.3 1113.76
  5138.4 1114.76  5158.5 1115.89  5163.6 1116.80  5198.6 1119.76  5218.7 1120.84
#Mann=4,-1,0
  4596.3    0.12       0  4608.2    0.05       0  4994.2    0.03       0
  4998.2    0.05       0
Bank Sta=4994.2,4998.2
Exp/Cntr=0.3,0.1

Type RM Length L Ch R = 1,23791,483,483,483
BEGIN DESCRIPTION:
BOARD BRANCH 44.0
END DESCRIPTION:
XS GIS Cut Line= 3
      2860455.65     10272653.09      2860159.50     10272466.00
      2859905.70     10272503.11
#Sta/Elev= 30
  4649.7 1116.90  4657.3 1116.22  4708.8 1115.03  4757.3 1113.11  4787.9 1113.00
  4809.1 1112.08  4882.0 1110.99  4909.9 1110.15  4924.4 1109.22  4933.5 1109.53
  4939.7 1109.23  4945.6 1107.93  4954.9 1107.68  4960.9 1108.04  4982.0 1106.87
  4995.3 1105.20  4995.6 1104.70  4999.1 1104.70  4999.3 1105.20  5004.5 1105.34
  5011.8 1107.42  5016.8 1106.49  5024.1 1108.09  5034.2 1109.15  5088.8 1110.91
  5145.3 1112.07  5189.1 1114.19  5189.2 1114.20  5216.1 1116.24  5256.5 1117.98
#Mann=6,-1,0
  4649.7    0.05       0  4995.3    0.03       0  4999.3    0.05       0
  5088.8    0.12       0  5189.1    0.05       0  5189.2    0.12       0
Bank Sta=4995.3,4999.3
Exp/Cntr=0.3,0.1

Type RM Length L Ch R = 1,23308,470,470,470
BEGIN DESCRIPTION:
BOARD BRANCH 43.0
END DESCRIPTION:
XS GIS Cut Line= 3
      2860355.65     10272103.11      2860052.75     10272129.00
      2859905.69     10272453.10
#Sta/Elev= 30
  4696.0 1114.75  4846.5 1110.79  4866.6 1110.63  4916.8 1108.58  4926.8 1108.62
  4936.8 1107.87  4946.9 1105.22  4956.9 1103.95  4985.8 1105.60  4990.8 1102.88
  4994.0 1102.39  4994.3 1101.89  4997.8 1101.89  4998.0 1102.39  5002.5 1102.39
  5007.5 1103.30  5015.5 1102.64  5025.1 1104.33  5030.6 1103.33  5037.5 1105.33
  5048.2 1106.42  5053.7 1106.19  5082.2 1107.03  5128.4 1106.62  5184.6 1107.54
  5213.2 1107.98  5290.4 1112.61  5301.0 1113.74  5312.0 1113.87  5355.9 1116.83
#Mann=5,-1,0
  4696.0    0.05       0  4994.0    0.05       0  4998.0    0.05       0
  5184.6    0.12       0  5290.4    0.05       0
Bank Sta=4994,4998
Exp/Cntr=0.3,0.1

Type RM Length L Ch R = 1,22838,489,489,489
BEGIN DESCRIPTION:
BOARD BRANCH 42.0
END DESCRIPTION:
XS GIS Cut Line= 3
      2860355.66     10271403.14      2859648.25     10272273.00
      2859755.66     10272403.09
#Sta/Elev= 30
  3878.8 1116.20  3949.9 1113.91  3964.2 1112.45  4013.8 1111.56  4483.5 1112.33
  4681.8 1111.29  4817.5 1106.90  4951.8 1104.27  4980.6 1102.83  4992.9 1100.56
  4993.2 1100.06  4996.9 1100.56  4998.1 1101.77  5005.2 1100.56  5013.1 1101.49
  5019.6 1101.04  5033.9 1106.78  5040.4 1105.79  5048.2 1108.23  5054.7 1105.31
  5062.6 1107.56  5069.1 1103.31  5076.9 1103.91  5083.4 1107.72  5097.7 1107.30
  5104.2 1109.06  5112.1 1108.67  5118.6 1111.31  5145.6 1113.63  5168.7 1115.78
#Mann=4,-1,0
  3878.8    0.05       0  4992.9    0.03       0  4996.9    0.05       0
  5145.6    0.12       0
Bank Sta=4992.9,4996.9
Exp/Cntr=0.3,0.1

Type RM Length L Ch R = 1,22349,471,471,471
BEGIN DESCRIPTION:
BOARD BRANCH 41.0
END DESCRIPTION:
XS GIS Cut Line= 3
      2859655.69     10271803.10      2859358.50     10272023.00
      2859355.68     10272503.09
#Sta/Elev= 30
  4630.3 1110.42  4687.7 1110.32  4773.3 1107.70  4787.9 1107.90  4794.1 1107.16
  4823.4 1106.54  4829.6 1105.68  4838.0 1105.86  4844.2 1104.76  4852.6 1105.15
  4858.9 1103.70  4866.7 1104.74  4873.5 1104.71  4879.7 1102.60  4888.1 1102.50
  4894.3 1101.33  4902.7 1101.51  4909.0 1099.82  4923.6 1100.45  4929.8 1099.68
  4986.3 1099.02  4986.6 1098.52  4990.3 1099.02  5002.6 1099.19  5010.1 1101.19
  5020.1 1102.11  5180.1 1103.59  5290.1 1105.43  5430.1 1113.40  5480.1 1114.96
#Mann=3,-1,0
  4630.3    0.05       0  4986.3    0.05       0  4990.3    0.05       0
Bank Sta=4986.3,4990.3
Exp/Cntr=0.3,0.1

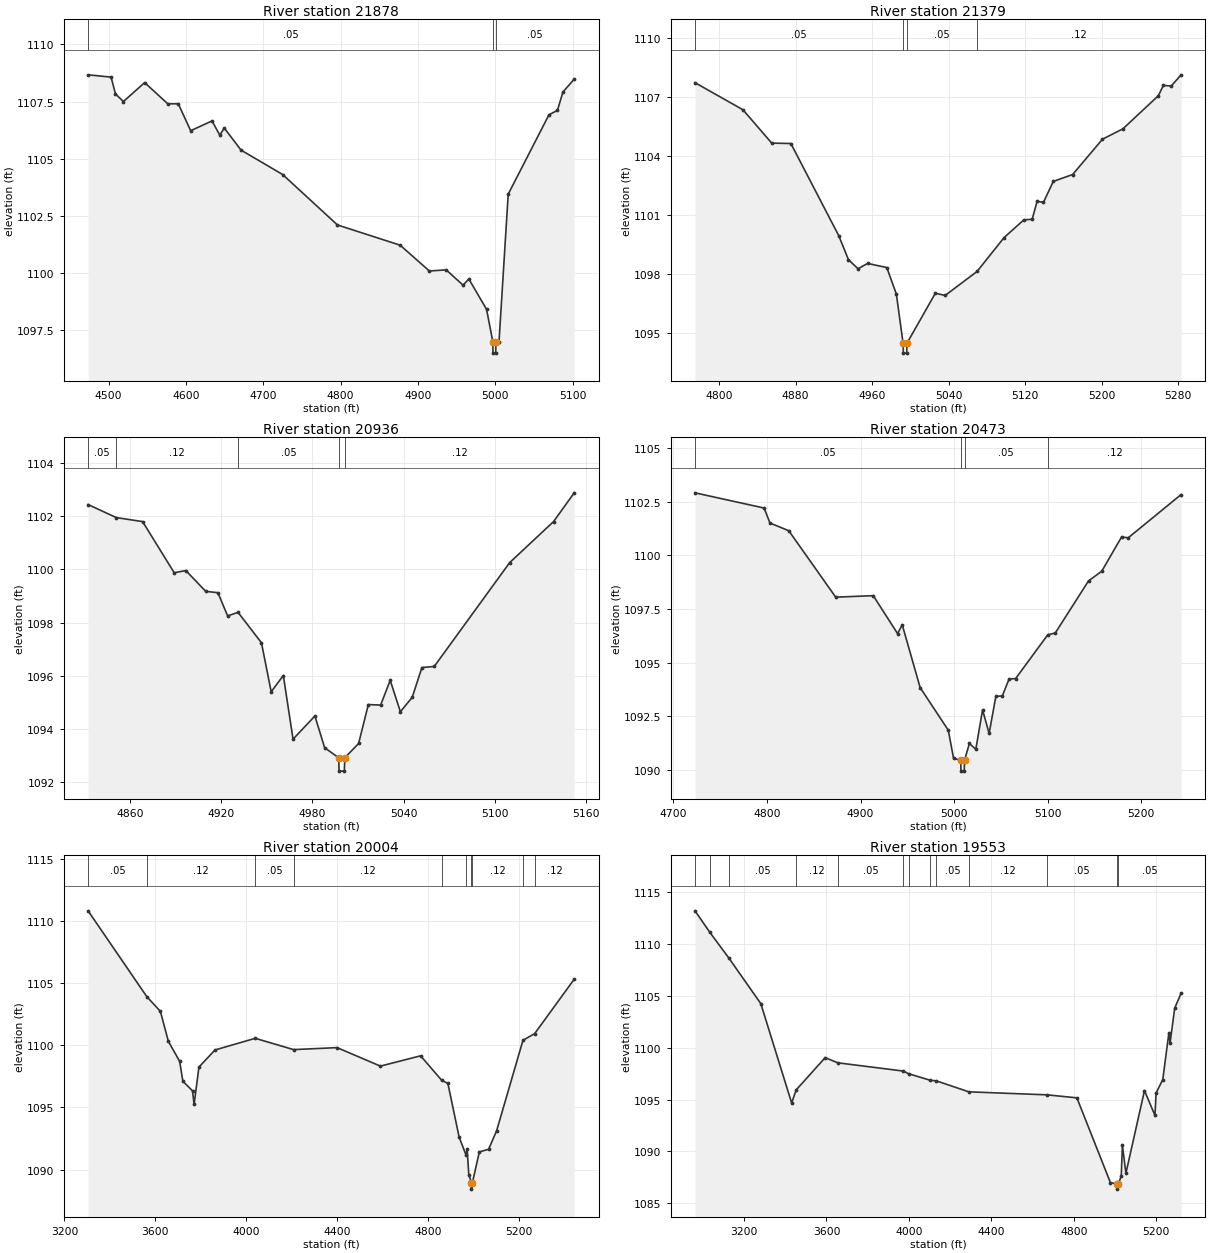
Type RM Length L Ch R = 1,21878,499,499,499
BEGIN DESCRIPTION:
BOARD BRANCH 40.0
END DESCRIPTION:
XS GIS Cut Line= 3
      2859305.67     10271853.14      2859049.50     10272313.00
      2858955.71     10272353.10
#Sta/Elev= 30
  4473.6 1108.67  4503.3 1108.57  4509.0 1107.83  4519.3 1107.50  4546.7 1108.33
  4576.6 1107.40  4590.2 1107.40  4606.2 1106.22  4633.8 1106.65  4643.9 1106.02
  4649.6 1106.34  4671.3 1105.37  4725.1 1104.30  4795.9 1102.09  4877.1 1101.20
  4914.8 1100.07  4936.5 1100.12  4958.3 1099.45  4965.8 1099.72  4988.7 1098.39
  4996.8 1096.97  4997.0 1096.47  5000.5 1096.47  5000.8 1096.97  5004.8 1096.97
  5016.7 1103.44  5069.4 1106.92  5080.3 1107.11  5087.5 1107.92  5102.0 1108.48
#Mann=3,-1,0
  4473.6    0.05       0  4996.8    0.05       0  5000.8    0.05       0
Bank Sta=4996.8,5000.8
Exp/Cntr=0.3,0.1

Type RM Length L Ch R = 1,21379,443,443,443
BEGIN DESCRIPTION:
BOARD BRANCH 39.0
END DESCRIPTION:
XS GIS Cut Line= 3
      2859205.69     10271853.11      2858981.00     10271838.00
      2858705.69     10271903.11
#Sta/Elev= 30
  4774.8 1107.73  4824.9 1106.35  4855.0 1104.65  4875.0 1104.63  4925.1 1099.93
  4935.2 1098.71  4945.2 1098.25  4955.2 1098.52  4975.3 1098.31  4985.3 1096.95
  4992.3 1094.45  4992.6 1093.95  4996.1 1093.95  4996.3 1094.45  5026.0 1097.00
  5036.3 1096.89  5069.6 1098.11  5097.9 1099.84  5118.5 1100.74  5127.2 1100.77
  5132.4 1101.69  5139.0 1101.63  5149.3 1102.70  5169.5 1103.05  5200.7 1104.85
  5222.1 1105.38  5259.2 1107.07  5264.3 1107.59  5272.6 1107.56  5282.9 1108.13
#Mann=4,-1,0
  4774.8    0.05       0  4992.3    0.05       0  4996.3    0.05       0
  5069.6    0.12       0
Bank Sta=4992.3,4996.3
Exp/Cntr=0.3,0.1

Type RM Length L Ch R = 1,20936,463,463,463
BEGIN DESCRIPTION:
BOARD BRANCH 38.0
END DESCRIPTION:
XS GIS Cut Line= 3
      2858905.68     10271453.12      2858775.50     10271559.00
      2858655.65     10271653.14
#Sta/Elev= 30
  4832.2 1102.43  4850.8 1101.94  4868.1 1101.79  4888.9 1099.87  4896.6 1099.95
  4909.7 1099.17  4917.7 1099.12  4924.1 1098.25  4931.0 1098.38  4946.4 1097.24
  4952.8 1095.40  4960.8 1096.01  4967.2 1093.62  4981.6 1094.49  4988.0 1093.30
  4997.3 1092.92  4997.5 1092.42  5001.0 1092.42  5001.3 1092.92  5010.4 1093.46
  5016.8 1094.92  5024.9 1094.90  5031.2 1095.83  5037.9 1094.65  5045.7 1095.19
  5052.1 1096.31  5060.2 1096.35  5109.9 1100.25  5138.8 1101.79  5152.4 1102.87
#Mann=5,-1,0
  4832.2    0.05       0  4850.8    0.12       0  4931.0    0.05       0
  4997.3    0.07       0  5001.3    0.12       0
Bank Sta=4997.3,5001.3
Exp/Cntr=0.3,0.1

Type RM Length L Ch R = 1,20473,469,469,469
BEGIN DESCRIPTION:
BOARD BRANCH 37.0
END DESCRIPTION:
XS GIS Cut Line= 3
      2858855.64     10271253.11      2858579.50     10271234.00
      2858405.69     10271403.11
#Sta/Elev= 30
  4723.2 1102.92  4797.0 1102.21  4803.3 1101.51  4823.4 1101.15  4873.5 1098.05
  4913.6 1098.12  4939.6 1096.35  4944.6 1096.76  4963.7 1093.83  4993.8 1091.84
  4999.4 1090.53  5007.1 1090.43  5007.3 1089.93  5010.8 1089.93  5011.1 1090.43
  5016.3 1091.22  5023.2 1090.95  5030.4 1092.79  5037.4 1091.69  5044.6 1093.42
  5051.5 1093.44  5058.7 1094.23  5065.7 1094.25  5100.0 1096.29  5108.1 1096.38
  5143.6 1098.81  5157.7 1099.26  5178.9 1100.86  5186.0 1100.82  5242.5 1102.84
#Mann=4,-1,0
  4723.2    0.05       0  5007.1    0.05       0  5011.1    0.05       0
  5100.0    0.12       0
Bank Sta=5007.1,5011.1
Exp/Cntr=0.3,0.1

Type RM Length L Ch R = 1,20004,451,451,451
BEGIN DESCRIPTION:
BOARD BRANCH 36.0
END DESCRIPTION:
XS GIS Cut Line= 3
      2859405.69     10269853.11      2858221.25     10271067.00
      2858305.68     10271503.10
#Sta/Elev= 30
  3304.0 1110.84  3562.3 1103.93  3622.3 1102.74  3657.5 1100.32  3707.1 1098.72
  3721.3 1097.11  3763.7 1096.34  3770.7 1095.25  3792.0 1098.25  3862.7 1099.63
  4039.9 1100.57  4208.6 1099.66  4400.1 1099.82  4591.0 1098.33  4767.9 1099.16
  4860.7 1097.19  4888.0 1096.94  4937.6 1092.61  4968.1 1091.16  4972.9 1091.64
  4980.1 1089.59  4991.8 1088.92  4992.0 1088.42  4995.8 1088.92  5026.6 1091.42
  5067.3 1091.63  5102.6 1093.12  5218.7 1100.41  5270.2 1100.95  5444.2 1105.33
#Mann=10,-1,0
  3304.0    0.05       0  3562.3    0.12       0  4039.9    0.05       0
  4208.6    0.12       0  4860.7    0.05       0  4968.1    0.12       0
  4991.8    0.07       0  4995.8    0.12       0  5218.7    0.05       0
  5270.2    0.12       0
Bank Sta=4991.8,4995.8
Exp/Cntr=0.3,0.1

Type RM Length L Ch R = 1,19553,463,463,463
BEGIN DESCRIPTION:
BOARD BRANCH 35.0
END DESCRIPTION:
XS GIS Cut Line= 3
      2859355.67     10269703.12      2857794.50     10271013.00
      2857505.69     10271153.11
#Sta/Elev= 30
  2962.1 1113.21  3034.6 1111.12  3127.2 1108.63  3281.5 1104.25  3431.0 1094.67
  3453.2 1095.93  3593.7 1099.04  3655.3 1098.54  3971.0 1097.75  3999.8 1097.48
  4104.7 1096.85  4133.2 1096.80  4290.7 1095.74  4670.5 1095.45  4815.2 1095.16
  4977.9 1086.98  5011.4 1086.85  5011.7 1086.35  5015.6 1086.85  5030.5 1087.58
  5036.1 1090.59  5053.1 1087.88  5143.2 1095.86  5194.1 1093.47  5199.7 1095.63
  5232.1 1096.93  5261.8 1101.45  5267.4 1100.45  5289.9 1103.82  5321.0 1105.26
#Mann=13,-1,0
  2962.1    0.05       0  3034.6    0.12       0  3127.2    0.05       0
  3453.2    0.12       0  3655.3    0.05       0  3971.0    0.12       0
  3999.8    0.05       0  4104.7    0.12       0  4133.2    0.05       0
  4290.7    0.12       0  4670.5    0.05       0  5011.4    0.05       0
  5015.6    0.05       0
Bank Sta=5011.4,5015.6
Exp/Cntr=0.3,0.1

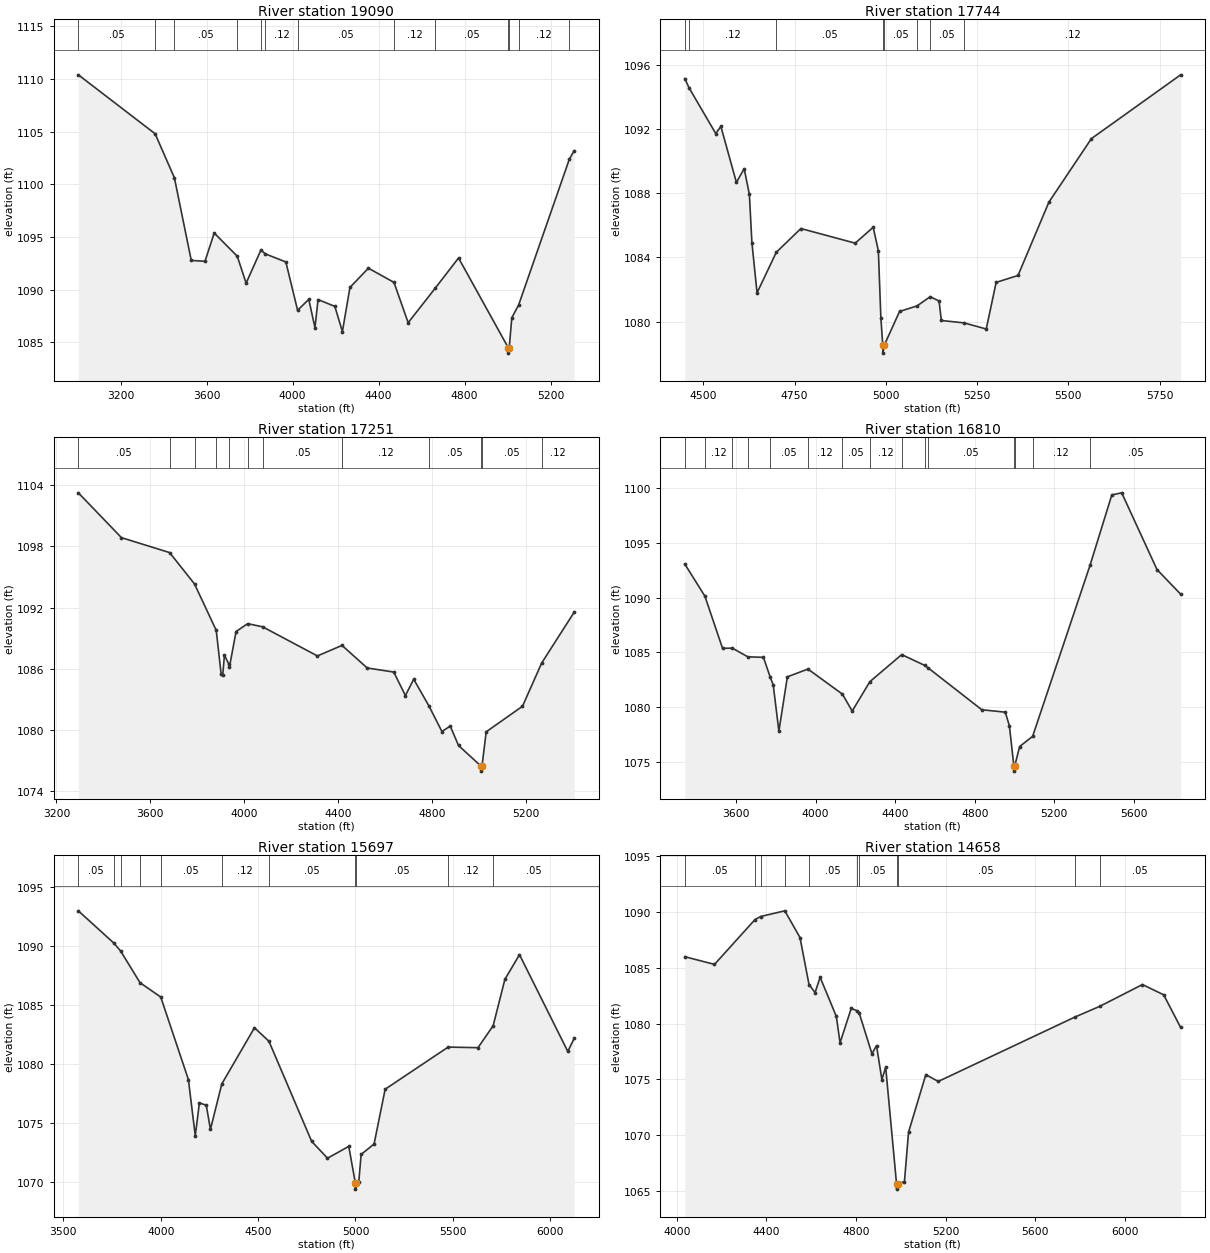
Type RM Length L Ch R = 1,19090,1346,1346,1346
BEGIN DESCRIPTION:
BOARD BRANCH 34.0
END DESCRIPTION:
XS GIS Cut Line= 3
      2859055.68     10269403.12      2857520.50     10270680.00
      2857305.70     10270903.10
#Sta/Elev= 30
  3003.2 1110.40  3360.5 1104.80  3450.2 1100.61  3528.5 1092.77  3592.3 1092.68
  3635.3 1095.37  3742.4 1093.17  3783.7 1090.61  3852.5 1093.75  3873.0 1093.39
  3968.6 1092.62  4023.2 1088.03  4075.3 1089.07  4104.0 1086.37  4118.3 1089.05
  4196.4 1088.40  4231.6 1086.01  4266.7 1090.20  4352.6 1092.03  4471.6 1090.68
  4537.5 1086.85  4663.5 1090.13  4771.9 1093.00  5003.5 1084.46  5003.8 1083.96
  5007.7 1084.46  5019.6 1087.32  5051.5 1088.54  5287.2 1102.38  5309.7 1103.19
#Mann=13,-1,0
  3003.2    0.05       0  3360.5    0.12       0  3450.2    0.05       0
  3742.4    0.12       0  3852.5    0.05       0  3873.0    0.12       0
  4023.2    0.05       0  4471.6    0.12       0  4663.5    0.05       0
  5003.5    0.05       0  5007.7    0.05       0  5051.5    0.12       0
  5287.2    0.05       0
Bank Sta=5003.5,5007.7
Exp/Cntr=0.3,0.1

Type RM Length L Ch R = 1,17744,493,493,493
BEGIN DESCRIPTION:
BOARD BRANCH 33.0
END DESCRIPTION:
XS GIS Cut Line= 3
      2857955.69     10269353.11      2857555.50     10269732.00
      2857105.69     10270403.10
#Sta/Elev= 30
  4448.9 1095.12  4461.1 1094.53  4533.7 1091.71  4547.8 1092.15  4590.3 1088.67
  4611.7 1089.52  4625.9 1087.92  4632.8 1084.93  4646.9 1081.80  4699.6 1084.32
  4767.1 1085.80  4915.9 1084.89  4965.3 1085.88  4979.4 1084.42  4986.3 1080.25
  4991.5 1078.55  4991.8 1078.05  4995.8 1078.55  5037.5 1080.64  5085.7 1080.99
  5121.7 1081.56  5145.8 1081.29  5152.1 1080.08  5214.5 1079.93  5275.1 1079.55
  5302.3 1082.45  5362.2 1082.88  5446.8 1087.44  5563.3 1091.39  5807.9 1095.36
#Mann=8,-1,0
  4448.9    0.05       0  4461.1    0.12       0  4699.6    0.05       0
  4991.5    0.05       0  4995.8    0.05       0  5085.7    0.12       0
  5121.7    0.05       0  5214.5    0.12       0
Bank Sta=4991.5,4995.8
Exp/Cntr=0.3,0.1

Type RM Length L Ch R = 1,17251,441,441,441
BEGIN DESCRIPTION:
BOARD BRANCH 32.0
END DESCRIPTION:
XS GIS Cut Line= 3
      2858305.70     10268553.10      2857092.00     10269753.00
      2857155.68     10270153.06
#Sta/Elev= 30
  3293.3 1103.23  3477.1 1098.84  3682.0 1097.38  3788.1 1094.31  3880.7 1089.76
  3901.4 1085.51  3908.5 1085.44  3915.6 1087.34  3933.2 1086.50  3936.8 1086.16
  3965.1 1089.65  4014.6 1090.42  4078.3 1090.11  4311.6 1087.26  4416.4 1088.29
  4523.7 1086.08  4636.8 1085.68  4686.3 1083.38  4721.7 1084.98  4785.9 1082.39
  4841.9 1079.86  4877.3 1080.39  4912.6 1078.49  5007.8 1076.48  5008.2 1075.98
  5012.6 1076.48  5030.5 1079.83  5185.0 1082.33  5266.9 1086.57  5405.1 1091.54
#Mann=12,-1,0
  3293.3    0.05       0  3682.0    0.12       0  3788.1    0.05       0
  3880.7    0.12       0  3933.2    0.05       0  4014.6    0.12       0
  4078.3    0.05       0  4416.4    0.12       0  4785.9    0.05       0
  5007.8    0.05       0  5012.6    0.05       0  5266.9    0.12       0
Bank Sta=5007.8,5012.6
Exp/Cntr=0.3,0.1

Type RM Length L Ch R = 1,16810,1113,1113,1113
BEGIN DESCRIPTION:
Mapping XS f9944834
END DESCRIPTION:
XS GIS Cut Line= 4
      2857845.95     10268494.99      2856699.47     10269526.82
      2856617.58     10269838.01      2856225.03     10270328.70
#Sta/Elev= 30
  3342.1 1093.08  3443.2 1090.14  3531.8 1085.38  3581.4 1085.39  3659.0 1084.60
  3737.4 1084.55  3771.4 1082.75  3786.7 1082.02  3815.1 1077.80  3857.7 1082.77
  3961.1 1083.48  4134.4 1081.19  4183.6 1079.64  4272.6 1082.33  4432.4 1084.80
  4549.1 1083.81  4565.9 1083.58  4835.3 1079.76  4953.1 1079.54  4973.8 1078.30
  4996.2 1074.65  4996.5 1074.15  5001.1 1074.65  5025.5 1076.40  5090.7 1077.33
  5379.2 1092.96  5488.8 1099.40  5538.5 1099.59  5716.1 1092.57  5834.7 1090.33
#Mann=15,-1,0
  3342.1    0.05       0  3443.2    0.12       0  3581.4    0.05       0
  3659.0    0.12       0  3771.4    0.05       0  3961.1    0.12       0
  4134.4    0.05       0  4272.6    0.12       0  4432.4    0.05       0
  4549.1    0.12       0  4565.9    0.05       0  4996.2    0.05       0
  5001.1    0.05       0  5090.7    0.12       0  5379.2    0.05       0
Bank Sta=4996.2,5001.1
Exp/Cntr=0.3,0.1

Type RM Length L Ch R = 1,15697,1039,1039,1039
BEGIN DESCRIPTION:
Mapping XS 1108fac4
END DESCRIPTION:
XS GIS Cut Line= 6
      2857633.03     10268331.21      2856977.91     10268969.96
      2856633.96     10268871.68      2856519.31     10269051.85
      2856240.88     10269461.31      2855962.42     10269952.70
#Sta/Elev= 30
  3576.7 1092.99  3758.9 1090.26  3793.3 1089.60  3893.7 1086.90  3999.9 1085.69
  4141.9 1078.70  4177.2 1073.94  4198.5 1076.73  4233.8 1076.52  4255.1 1074.48
  4313.4 1078.33  4481.3 1083.09  4555.6 1081.94  4774.8 1073.47  4856.2 1072.04
  4965.5 1073.04  4999.4 1069.92  4999.8 1069.42  5004.4 1069.92  5017.0 1070.06
  5029.0 1072.36  5095.4 1073.24  5152.3 1077.88  5475.8 1081.45  5629.1 1081.40
  5706.9 1083.26  5767.1 1087.18  5842.1 1089.28  6090.2 1081.08  6122.9 1082.18
#Mann=11,-1,0
  3576.7    0.05       0  3758.9    0.12       0  3793.3    0.05       0
  3893.7    0.12       0  3999.9    0.05       0  4313.4    0.12       0
  4555.6    0.05       0  4999.4    0.03       0  5004.4    0.05       0
  5475.8    0.12       0  5706.9    0.05       0
Bank Sta=4999.4,5004.4
Exp/Cntr=0.3,0.1

Type RM Length L Ch R = 1,14658,648,648,648
BEGIN DESCRIPTION:
Mapping XS b0a71159
END DESCRIPTION:
XS GIS Cut Line= 4
      2856748.60     10267725.22      2856388.28     10268429.47
      2856273.63     10268986.33      2855815.04     10269706.98
#Sta/Elev= 30
  4035.7 1086.00  4168.3 1085.31  4348.9 1089.33  4374.3 1089.61  4482.3 1090.12
  4550.0 1087.72  4590.3 1083.50  4617.4 1082.78  4639.9 1084.15  4712.3 1080.64
  4728.9 1078.27  4779.0 1081.37  4806.2 1081.13  4813.7 1080.99  4871.3 1077.28
  4891.7 1078.02  4915.7 1074.96  4932.6 1076.08  4981.0 1065.63  4981.4 1065.13
  4986.2 1065.63  5016.3 1065.79  5034.7 1070.24  5111.8 1075.41  5167.4 1074.80
  5777.4 1080.58  5889.1 1081.55  6079.0 1083.50  6173.8 1082.58  6249.5 1079.65
#Mann=11,-1,0
  4035.7    0.05       0  4348.9    0.12       0  4374.3    0.05       0
  4482.3    0.12       0  4590.3    0.05       0  4806.2    0.12       0
  4813.7    0.05       0  4981.0    0.05       0  4986.2    0.05       0
  5777.4    0.12       0  5889.1    0.05       0
Bank Sta=4981,4986.2
Exp/Cntr=0.3,0.1