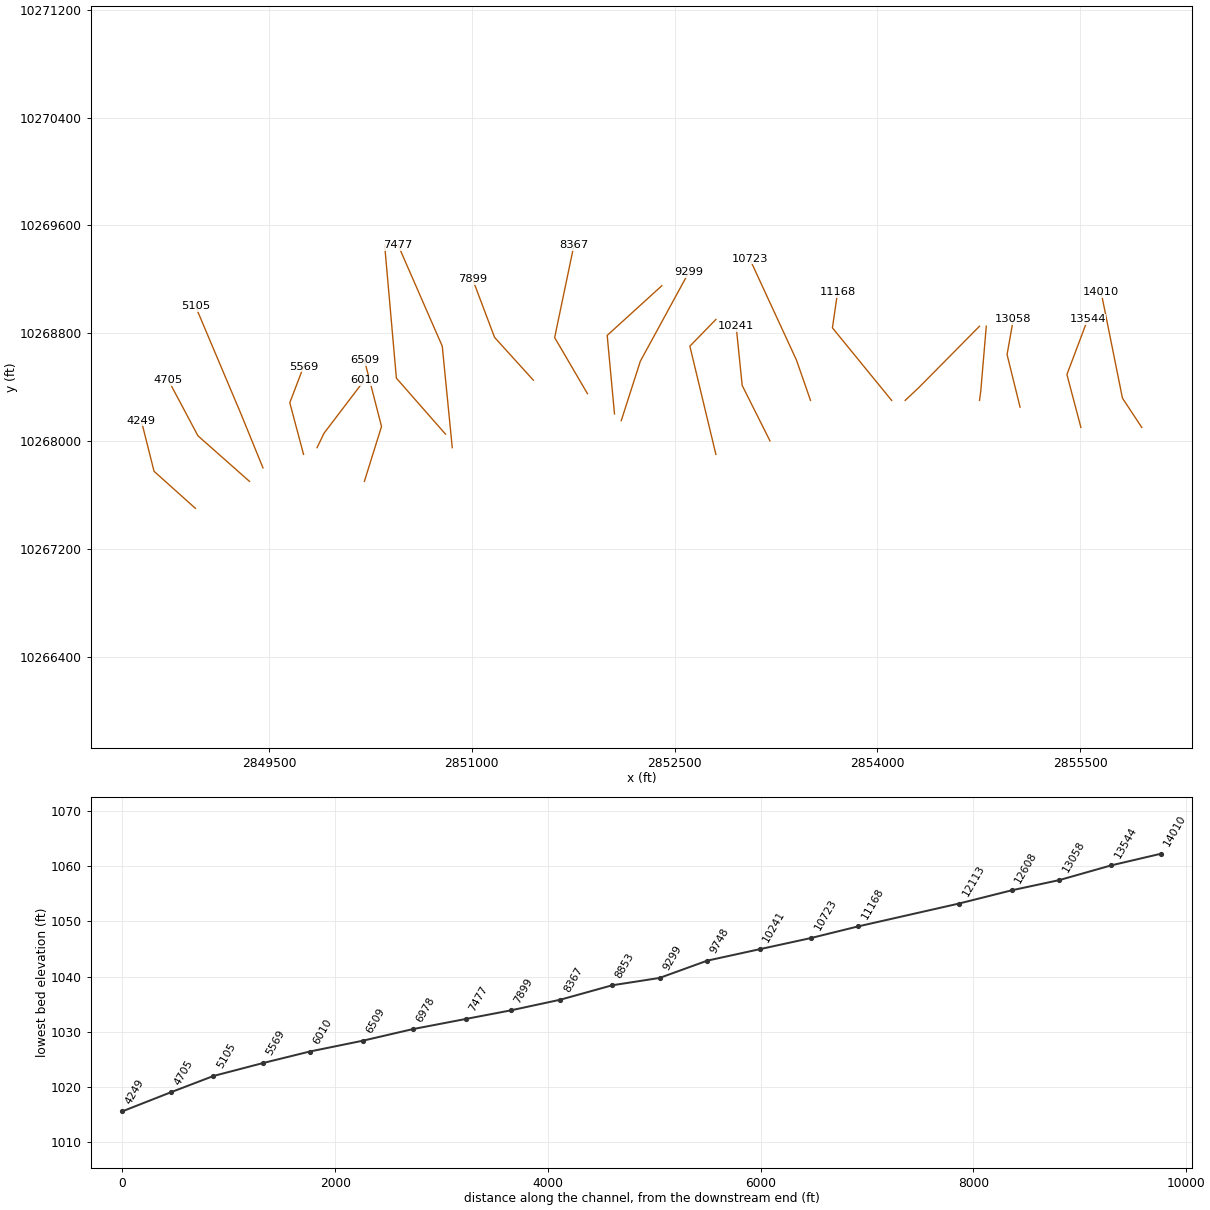
HEC-RAS study BOARD BRANCH.prj: BOARD BRANCH Base Level Engineering

--- BOARD BRANCH.g01 (geometry) --- (continued)

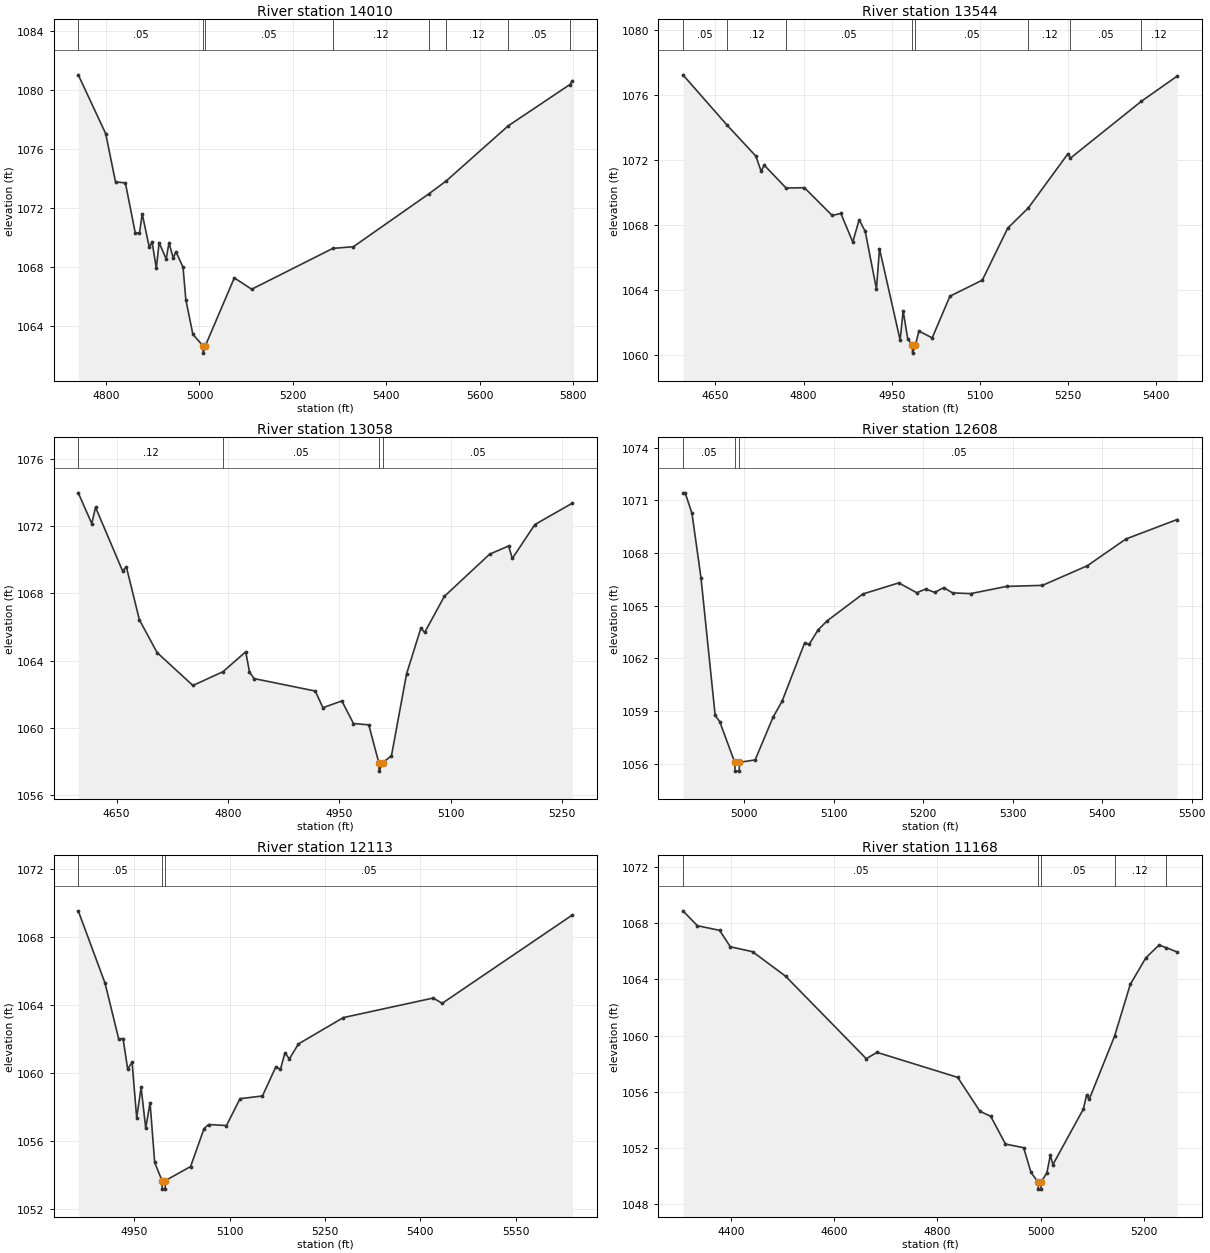
Type RM Length L Ch R = 1,14010,466,466,466
BEGIN DESCRIPTION:
BOARD BRANCH 28.0
END DESCRIPTION:
XS GIS Cut Line= 3
      2855955.68     10268103.12      2855813.00     10268320.00
      2855655.68     10269103.15
#Sta/Elev= 30
  4740.4 1081.05  4799.2 1077.06  4820.2 1073.79  4841.3 1073.73  4862.4 1070.36
  4871.5 1070.30  4877.4 1071.63  4892.5 1069.37  4898.5 1069.72  4907.6 1067.94
  4913.6 1069.68  4928.7 1068.57  4934.7 1069.66  4943.8 1068.64  4949.7 1069.06
  4964.8 1068.01  4970.8 1065.81  4985.9 1063.46  5007.4 1062.69  5007.8 1062.19
  5012.6 1062.69  5074.6 1067.29  5111.8 1066.52  5285.7 1069.29  5329.6 1069.40
  5491.5 1072.99  5528.5 1073.86  5661.5 1077.60  5793.2 1080.39  5798.8 1080.65
#Mann=8,-1,0
  4740.4    0.05       0  5007.4    0.03       0  5012.6    0.05       0
  5285.7    0.12       0  5491.5    0.05       0  5528.5    0.12       0
  5661.5    0.05       0  5793.2    0.12       0
Bank Sta=5007.4,5012.6
Exp/Cntr=0.3,0.1

Type RM Length L Ch R = 1,13544,486,486,486
BEGIN DESCRIPTION:
BOARD BRANCH 27.0
END DESCRIPTION:
XS GIS Cut Line= 3
      2855505.68     10268103.12      2855402.25     10268495.00
      2855555.68     10268903.11
#Sta/Elev= 30
  4594.7 1077.25  4669.8 1074.15  4718.8 1072.24  4727.9 1071.30  4733.1 1071.68
  4770.3 1070.27  4801.5 1070.29  4848.7 1068.58  4863.6 1068.70  4883.8 1066.94
  4894.6 1068.31  4905.0 1067.60  4924.1 1064.04  4929.3 1066.53  4964.4 1060.90
  4969.6 1062.69  4977.4 1060.97  4985.1 1060.59  4985.5 1060.09  4990.4 1060.59
  4996.4 1061.45  5019.0 1061.03  5049.2 1063.60  5104.3 1064.59  5147.5 1067.79
  5182.8 1069.05  5250.2 1072.39  5254.2 1072.11  5375.1 1075.62  5436.0 1077.17
#Mann=8,-1,0
  4594.7    0.05       0  4669.8    0.12       0  4770.3    0.05       0
  4985.1    0.05       0  4990.4    0.05       0  5182.8    0.12       0
  5254.2    0.05       0  5375.1    0.12       0
Bank Sta=4985.1,4990.4
Exp/Cntr=0.3,0.1

Type RM Length L Ch R = 1,13058,450,450,450
BEGIN DESCRIPTION:
BOARD BRANCH 26.0
END DESCRIPTION:
XS GIS Cut Line= 3
      2855055.69     10268253.09      2854959.50     10268643.00
      2855005.69     10268903.13
#Sta/Elev= 30
  4598.4 1073.98  4616.6 1072.15  4621.7 1073.12  4658.1 1069.34  4663.2 1069.58
  4680.8 1066.43  4704.7 1064.48  4752.9 1062.53  4793.4 1063.35  4824.0 1064.53
  4829.1 1063.33  4835.3 1062.94  4917.7 1062.20  4928.0 1061.21  4953.5 1061.61
  4969.2 1060.27  4989.8 1060.19  5003.3 1057.94  5003.7 1057.44  5008.6 1057.94
  5020.4 1058.36  5040.7 1063.22  5060.0 1065.94  5065.1 1065.68  5091.5 1067.82
  5152.5 1070.33  5178.1 1070.82  5183.2 1070.08  5213.4 1072.09  5264.2 1073.37
#Mann=4,-1,0
  4598.4    0.12       0  4793.4    0.05       0  5003.3    0.03       0
  5008.6    0.05       0
Bank Sta=5003.3,5008.6
Exp/Cntr=0.3,0.1

Type RM Length L Ch R = 1,12608,495,495,495
BEGIN DESCRIPTION:
BOARD BRANCH 25.0
END DESCRIPTION:
XS GIS Cut Line= 3
      2854755.69     10268303.14      2854765.00     10268371.00
      2854805.68     10268853.09
#Sta/Elev= 30
  4931.5 1071.43  4934.0 1071.43  4941.6 1070.26  4951.7 1066.58  4967.5 1058.76
  4972.6 1058.40  4989.4 1056.08  4989.8 1055.58  4994.3 1055.58  4994.7 1056.08
  5012.2 1056.22  5032.2 1058.65  5042.3 1059.56  5067.5 1062.88  5072.5 1062.80
  5082.4 1063.61  5092.4 1064.13  5132.6 1065.67  5172.7 1066.30  5192.8 1065.74
  5202.8 1065.95  5212.9 1065.76  5222.9 1066.03  5232.9 1065.73  5253.0 1065.69
  5293.1 1066.10  5333.3 1066.16  5383.5 1067.28  5426.5 1068.80  5483.8 1069.91
#Mann=3,-1,0
  4931.5    0.05       0  4989.4    0.03       0  4994.7    0.05       0
Bank Sta=4989.4,4994.7
Exp/Cntr=0.3,0.1

Type RM Length L Ch R = 1,12113,945,945,945
BEGIN DESCRIPTION:
BOARD BRANCH 24.0
END DESCRIPTION:
XS GIS Cut Line= 3
      2854205.72     10268303.14      2854306.50     10268398.00
      2854755.65     10268853.08
#Sta/Elev= 30
  4861.6 1069.56  4903.8 1065.30  4925.3 1062.02  4932.1 1062.05  4939.4 1060.25
  4946.3 1060.66  4953.6 1057.37  4960.5 1059.18  4967.8 1056.77  4974.6 1058.28
  4981.9 1054.76  4993.4 1053.69  4993.8 1053.19  4998.3 1053.19  4998.7 1053.69
  5038.4 1054.52  5059.6 1056.75  5066.7 1056.99  5094.9 1056.93  5116.2 1058.51
  5151.5 1058.67  5172.8 1060.40  5179.8 1060.23  5186.9 1061.21  5193.9 1060.85
  5208.1 1061.73  5278.8 1063.28  5420.2 1064.43  5434.4 1064.12  5639.4 1069.32
#Mann=3,-1,0
  4861.6    0.05       0  4993.4    0.03       0  4998.7    0.05       0
Bank Sta=4993.4,4998.7
Exp/Cntr=0.3,0.1

Type RM Length L Ch R = 1,11168,445,445,445
BEGIN DESCRIPTION:
BOARD BRANCH 23.0
END DESCRIPTION:
XS GIS Cut Line= 3
      2854105.67     10268303.13      2853667.75     10268841.00
      2853705.68     10269103.07
#Sta/Elev= 30
  4306.4 1068.89  4334.4 1067.83  4377.5 1067.50  4398.3 1066.33  4441.4 1065.98
  4505.3 1064.24  4661.9 1058.36  4682.7 1058.81  4839.2 1057.03  4882.4 1054.61
  4903.2 1054.26  4931.9 1052.28  4967.1 1052.02  4981.4 1050.26  4995.2 1049.57
  4995.7 1049.07  5000.6 1049.07  5001.1 1049.57  5012.2 1050.24  5018.9 1051.48
  5023.9 1050.82  5083.0 1054.78  5089.2 1055.77  5094.2 1055.46  5143.5 1059.97
  5173.9 1063.65  5204.2 1065.55  5229.7 1066.45  5243.4 1066.27  5264.8 1065.96
#Mann=5,-1,0
  4306.4    0.05       0  4995.2    0.03       0  5001.1    0.05       0
  5143.5    0.12       0  5243.4    0.05       0
Bank Sta=4995.2,5001.1
Exp/Cntr=0.3,0.1

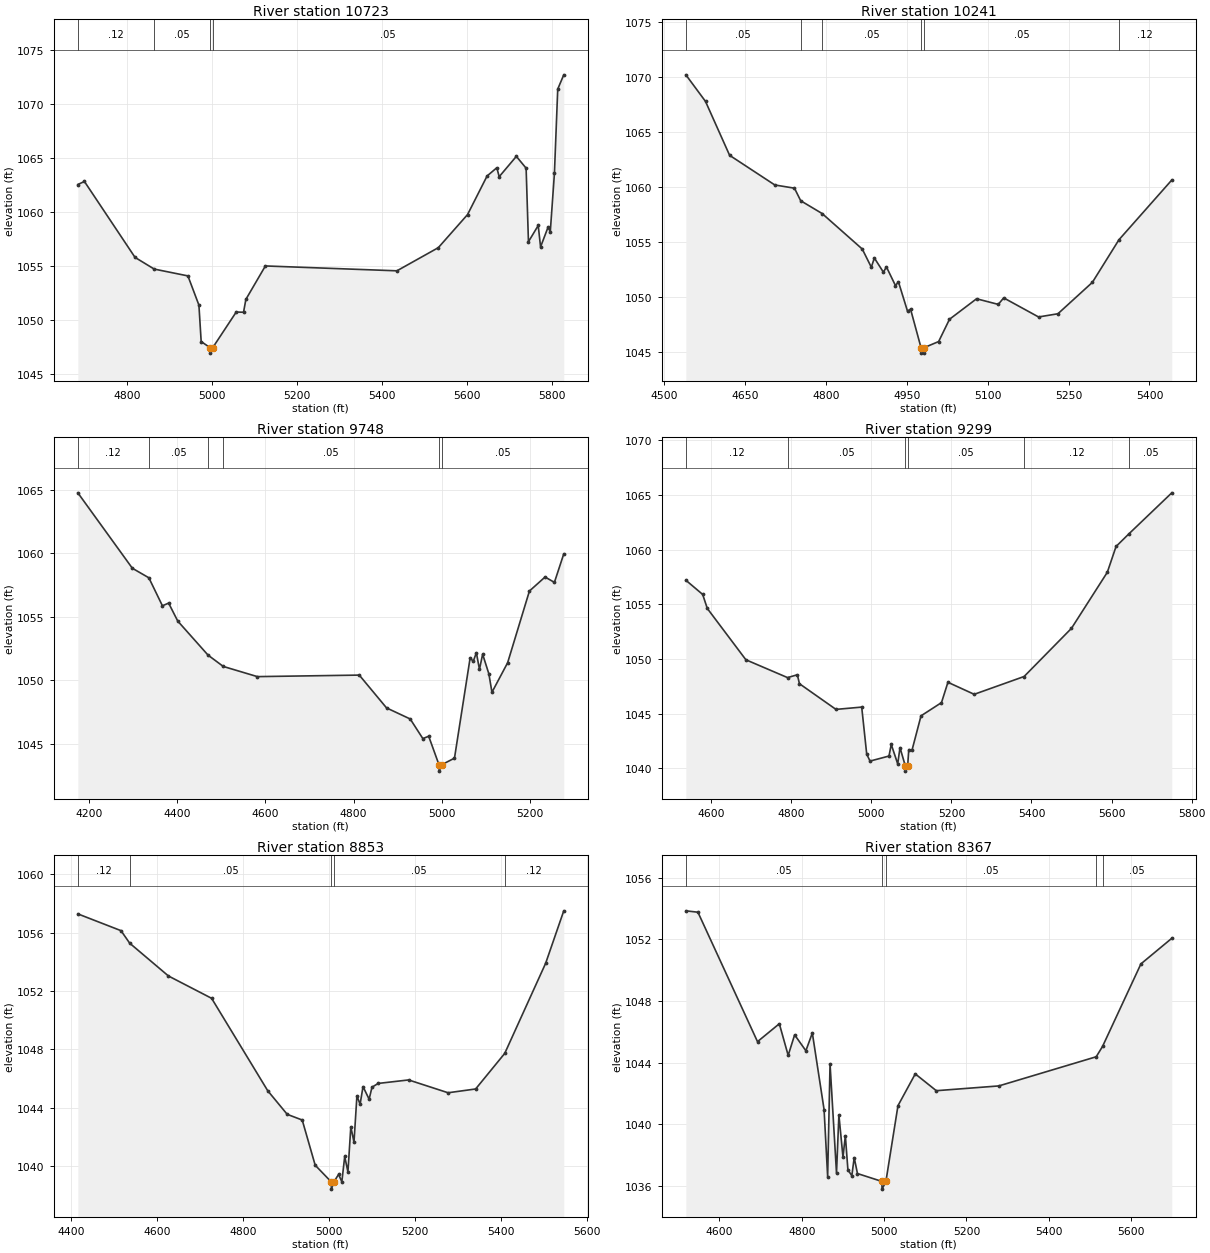
Type RM Length L Ch R = 1,10723,482,482,482
BEGIN DESCRIPTION:
BOARD BRANCH 22.0
END DESCRIPTION:
XS GIS Cut Line= 3
      2853505.67     10268303.15      2853401.75     10268602.00
      2853055.68     10269353.11
#Sta/Elev= 30
  4683.6 1062.55  4699.1 1062.83  4818.2 1055.81  4863.4 1054.73  4942.6 1054.10
  4968.5 1051.40  4973.8 1048.03  4995.0 1047.46  4995.5 1046.96  5000.9 1047.46
  5056.3 1050.76  5073.5 1050.74  5079.0 1051.93  5124.9 1055.02  5434.4 1054.57
  5531.8 1056.71  5600.6 1059.77  5646.6 1063.34  5669.5 1064.10  5675.0 1063.27
  5715.4 1065.15  5738.4 1064.06  5743.9 1057.26  5766.9 1058.76  5772.4 1056.78
  5789.8 1058.58  5795.3 1058.20  5805.0 1063.58  5812.8 1071.37  5827.0 1072.69
#Mann=4,-1,0
  4683.6    0.12       0  4863.4    0.05       0  4995.0    0.03       0
  5000.9    0.05       0
Bank Sta=4995,5000.9
Exp/Cntr=0.3,0.1

Type RM Length L Ch R = 1,10241,493,493,493
BEGIN DESCRIPTION:
BOARD BRANCH 21.0
END DESCRIPTION:
XS GIS Cut Line= 3
      2853205.69     10268003.10      2853000.25     10268414.00
      2852955.68     10268853.14
#Sta/Elev= 30
  4540.6 1070.18  4577.0 1067.77  4621.7 1062.88  4705.5 1060.19  4741.9 1059.90
  4753.5 1058.76  4793.2 1057.60  4867.6 1054.38  4884.4 1052.73  4890.0 1053.57
  4906.8 1052.28  4912.4 1052.76  4929.1 1051.07  4934.7 1051.40  4951.5 1048.74
  4957.1 1048.93  4976.5 1045.44  4977.0 1044.94  4982.0 1044.94  4982.4 1045.44
  5009.2 1045.99  5029.3 1048.01  5079.5 1049.87  5119.7 1049.36  5129.8 1049.95
  5194.4 1048.22  5230.3 1048.51  5294.2 1051.36  5343.4 1055.22  5441.4 1060.64
#Mann=6,-1,0
  4540.6    0.05       0  4753.5    0.12       0  4793.2    0.05       0
  4976.5    0.03       0  4982.4    0.05       0  5343.4    0.12       0
Bank Sta=4976.5,4982.4
Exp/Cntr=0.3,0.1

Type RM Length L Ch R = 1,9748,449,449,449
BEGIN DESCRIPTION:
BOARD BRANCH 20.0
END DESCRIPTION:
XS GIS Cut Line= 3
      2852805.69     10267903.07      2852613.25     10268705.00
      2852805.69     10268903.12
#Sta/Elev= 30
  4175.3 1064.75  4298.8 1058.82  4336.2 1058.07  4366.9 1055.87  4381.0 1056.08
  4401.6 1054.67  4470.3 1051.99  4504.8 1051.10  4582.0 1050.30  4812.9 1050.42
  4874.7 1047.84  4928.3 1046.97  4956.9 1045.43  4970.2 1045.61  4993.5 1043.37
  4994.0 1042.87  4999.5 1043.37  5028.6 1043.89  5064.1 1051.78  5071.1 1051.50
  5078.2 1052.18  5085.2 1050.87  5092.4 1052.06  5106.5 1050.52  5113.5 1049.07
  5149.0 1051.39  5198.4 1057.03  5233.8 1058.13  5255.0 1057.71  5276.2 1059.95
#Mann=6,-1,0
  4175.3    0.12       0  4336.2    0.05       0  4470.3    0.12       0
  4504.8    0.05       0  4993.5    0.03       0  4999.5    0.05       0
Bank Sta=4993.5,4999.5
Exp/Cntr=0.3,0.1

Type RM Length L Ch R = 1,9299,446,446,446
BEGIN DESCRIPTION:
BOARD BRANCH 19.0
END DESCRIPTION:
XS GIS Cut Line= 3
      2852105.68     10268153.09      2852247.00     10268594.00
      2852605.69     10269253.12
#Sta/Elev= 30
  4537.0 1057.21  4579.0 1055.91  4590.5 1054.63  4686.9 1049.93  4790.9 1048.30
  4815.4 1048.56  4820.6 1047.74  4911.8 1045.39  4976.1 1045.60  4988.6 1041.29
  4996.9 1040.66  5044.2 1041.12  5049.9 1042.18  5066.0 1040.40  5071.7 1041.89
  5084.8 1040.24  5085.3 1039.74  5090.9 1040.24  5093.6 1041.71  5101.5 1041.63
  5124.2 1044.80  5175.3 1046.01  5191.4 1047.87  5257.0 1046.77  5381.6 1048.40
  5499.9 1052.81  5589.4 1057.94  5611.2 1060.30  5643.4 1061.46  5750.4 1065.21
#Mann=6,-1,0
  4537.0    0.12       0  4790.9    0.05       0  5084.8    0.03       0
  5090.9    0.05       0  5381.6    0.12       0  5643.4    0.05       0
Bank Sta=5084.8,5090.9
Exp/Cntr=0.3,0.1

Type RM Length L Ch R = 1,8853,486,486,486
BEGIN DESCRIPTION:
BOARD BRANCH 18.0
END DESCRIPTION:
XS GIS Cut Line= 3
      2852055.69     10268203.09      2852001.75     10268785.00
      2852405.68     10269153.11
#Sta/Elev= 30
  4415.6 1057.29  4516.0 1056.14  4536.3 1055.28  4626.5 1053.03  4726.9 1051.50
  4857.5 1045.16  4902.9 1043.54  4937.8 1043.15  4968.0 1040.05  5005.3 1038.91
  5005.8 1038.41  5011.4 1038.91  5022.5 1039.42  5030.0 1038.91  5036.7 1040.65
  5044.2 1039.59  5050.9 1042.69  5058.3 1041.63  5065.1 1044.81  5072.5 1044.23
  5079.3 1045.44  5093.5 1044.58  5100.2 1045.40  5114.4 1045.66  5185.4 1045.90
  5277.3 1045.02  5341.4 1045.28  5409.1 1047.72  5504.3 1053.90  5546.5 1057.50
#Mann=5,-1,0
  4415.6    0.12       0  4536.3    0.05       0  5005.3    0.05       0
  5011.4    0.05       0  5409.1    0.12       0
Bank Sta=5005.3,5011.4
Exp/Cntr=0.3,0.1

Type RM Length L Ch R = 1,8367,468,468,468
BEGIN DESCRIPTION:
BOARD BRANCH 17.0
END DESCRIPTION:
XS GIS Cut Line= 3
      2851855.68     10268353.13      2851613.00     10268769.00
      2851755.68     10269453.08
#Sta/Elev= 30
  4518.5 1053.85  4547.8 1053.76  4692.5 1045.37  4745.5 1046.53  4767.0 1044.48
  4782.7 1045.81  4810.0 1044.78  4825.7 1045.93  4854.2 1040.97  4862.9 1036.62
  4868.7 1043.92  4884.4 1036.85  4890.2 1040.62  4900.1 1037.89  4905.9 1039.27
  4912.1 1037.06  4921.6 1036.68  4927.4 1037.85  4935.3 1036.82  4994.6 1036.31
  4995.1 1035.81  5004.4 1036.31  5033.7 1041.22  5075.7 1043.28  5126.8 1042.19
  5278.7 1042.50  5515.2 1044.39  5530.6 1045.06  5623.8 1050.41  5698.8 1052.07
#Mann=5,-1,0
  4518.5    0.05       0  4994.6    0.05       0  5004.4    0.05       0
  5515.2    0.12       0  5530.6    0.05       0
Bank Sta=4994.6,5004.4
Exp/Cntr=0.3,0.1

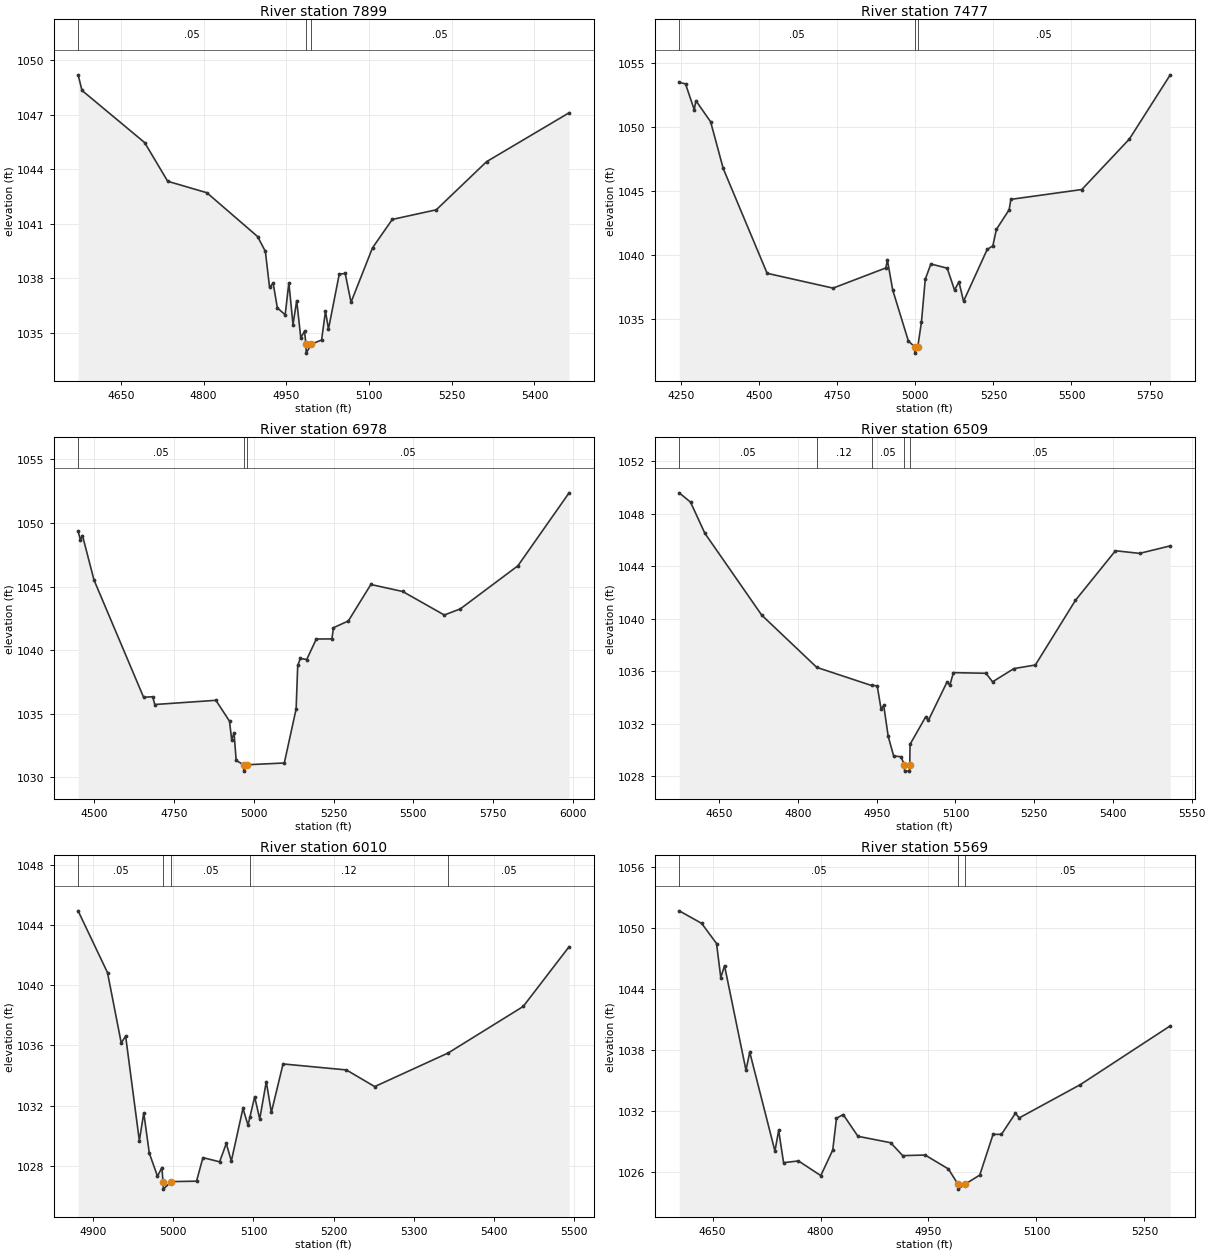
Type RM Length L Ch R = 1,7899,422,422,422
BEGIN DESCRIPTION:
BOARD BRANCH 16.0
END DESCRIPTION:
XS GIS Cut Line= 3
      2851455.69     10268453.11      2851168.75     10268770.00
      2851005.68     10269203.12
#Sta/Elev= 30
  4572.5 1049.19  4579.6 1048.33  4693.2 1045.46  4735.0 1043.33  4806.0 1042.70
  4897.9 1040.29  4912.1 1039.47  4919.6 1037.51  4926.3 1037.71  4933.8 1036.36
  4948.0 1035.98  4954.7 1037.74  4962.2 1035.44  4968.9 1036.76  4976.3 1034.71
  4983.1 1035.08  4985.6 1034.37  4986.1 1033.87  4995.5 1034.37  5014.0 1034.59
  5021.1 1036.18  5026.5 1035.19  5046.0 1038.21  5056.8 1038.26  5067.4 1036.67
  5106.4 1039.67  5142.2 1041.23  5222.0 1041.76  5313.2 1044.41  5462.8 1047.10
#Mann=3,-1,0
  4572.5    0.05       0  4985.6    0.03       0  4995.5    0.05       0
Bank Sta=4985.6,4995.5
Exp/Cntr=0.3,0.1

Type RM Length L Ch R = 1,7477,499,499,499
BEGIN DESCRIPTION:
BOARD BRANCH 15.0
END DESCRIPTION:
XS GIS Cut Line= 3
      2850855.68     10267953.13      2850781.75     10268705.00
      2850455.68     10269453.13
#Sta/Elev= 30
  4244.5 1053.52  4264.6 1053.40  4292.6 1051.37  4297.7 1052.09  4345.0 1050.43
  4385.2 1046.78  4525.8 1038.57  4736.8 1037.41  4905.7 1038.99  4910.7 1039.61
  4927.8 1037.26  4978.0 1033.26  4998.1 1032.82  4998.6 1032.32  5008.0 1032.82
  5019.8 1034.76  5031.9 1038.10  5049.9 1039.30  5102.2 1038.97  5125.6 1037.26
  5139.8 1037.90  5154.5 1036.38  5230.2 1040.44  5248.2 1040.72  5259.7 1042.01
  5300.5 1043.55  5305.9 1044.36  5533.1 1045.13  5685.2 1049.08  5816.1 1054.11
#Mann=3,-1,0
  4244.5    0.05       0  4998.1    0.03       0  5008.0    0.05       0
Bank Sta=4998.1,5008
Exp/Cntr=0.3,0.1

Type RM Length L Ch R = 1,6978,469,469,469
BEGIN DESCRIPTION:
BOARD BRANCH 14.0
END DESCRIPTION:
XS GIS Cut Line= 3
      2850805.69     10268053.11      2850442.50     10268468.00
      2850355.69     10269453.08
#Sta/Elev= 30
  4448.6 1049.36  4455.7 1048.68  4462.4 1049.01  4498.4 1045.52  4654.1 1036.29
  4682.6 1036.33  4689.2 1035.72  4880.9 1036.05  4923.6 1034.41  4930.3 1032.96
  4937.9 1033.48  4944.5 1031.32  4967.9 1030.98  4968.4 1030.48  4978.0 1030.98
  5095.5 1031.12  5132.6 1035.37  5137.6 1038.79  5145.7 1039.34  5165.8 1039.26
  5195.9 1040.87  5244.8 1040.88  5249.8 1041.76  5296.3 1042.29  5367.0 1045.16
  5466.9 1044.61  5597.4 1042.76  5647.6 1043.24  5828.3 1046.63  5988.9 1052.37
#Mann=3,-1,0
  4448.6    0.05       0  4967.9    0.03       0  4978.0    0.05       0
Bank Sta=4967.9,4978
Exp/Cntr=0.3,0.1

Type RM Length L Ch R = 1,6509,499,499,499
BEGIN DESCRIPTION:
BOARD BRANCH 13.0
END DESCRIPTION:
XS GIS Cut Line= 3
      2850205.68     10267703.10      2850332.50     10268110.00
      2850205.67     10268603.15
#Sta/Elev= 30
  4573.8 1049.58  4595.3 1048.87  4622.6 1046.50  4730.9 1040.27  4835.8 1036.29
  4940.1 1034.91  4950.9 1034.89  4958.2 1033.14  4963.4 1033.39  4971.8 1031.05
  4982.3 1029.54  4996.0 1029.49  5002.7 1028.89  5003.2 1028.39  5012.4 1028.39
  5012.9 1028.89  5013.5 1030.43  5043.4 1032.53  5048.6 1032.27  5084.1 1035.19
  5089.3 1034.93  5096.1 1035.89  5158.1 1035.84  5170.7 1035.19  5211.5 1036.20
  5252.2 1036.47  5328.5 1041.39  5404.8 1045.17  5450.7 1044.97  5509.2 1045.54
#Mann=5,-1,0
  4573.8    0.05       0  4835.8    0.12       0  4940.1    0.05       0
  5002.7    0.03       0  5012.9    0.05       0
Bank Sta=5002.7,5012.9
Exp/Cntr=0.3,0.1

Type RM Length L Ch R = 1,6010,441,441,441
BEGIN DESCRIPTION:
BOARD BRANCH 12.0
END DESCRIPTION:
XS GIS Cut Line= 3
      2849855.67     10267953.09      2849907.25     10268060.00
      2850205.71     10268453.14
#Sta/Elev= 30
  4881.3 1044.97  4918.0 1040.85  4935.1 1036.17  4940.6 1036.62  4957.7 1029.65
  4963.2 1031.51  4970.1 1028.83  4980.3 1027.29  4985.8 1027.87  4987.2 1026.93
  4987.7 1026.43  4997.5 1026.93  5029.0 1026.96  5037.0 1028.53  5057.8 1028.25
  5066.1 1029.47  5072.4 1028.30  5086.9 1031.81  5093.2 1030.69  5095.6 1031.24
  5101.5 1032.58  5107.8 1031.10  5116.0 1033.59  5122.3 1031.54  5136.9 1034.77
  5215.9 1034.37  5251.2 1033.26  5342.8 1035.50  5436.4 1038.60  5493.6 1042.58
#Mann=5,-1,0
  4881.3    0.05       0  4987.2    0.03       0  4997.5    0.05       0
  5095.6    0.12       0  5342.8    0.05       0
Bank Sta=4987.2,4997.5
Exp/Cntr=0.3,0.1

Type RM Length L Ch R = 1,5569,464,464,464
BEGIN DESCRIPTION:
BOARD BRANCH 11.0
END DESCRIPTION:
XS GIS Cut Line= 3
      2849755.69     10267903.07      2849654.00     10268286.00
      2849755.68     10268553.10
#Sta/Elev= 30
  4603.8 1051.68  4634.9 1050.45  4655.6 1048.47  4661.5 1045.12  4666.7 1046.29
  4696.5 1036.02  4701.7 1037.80  4736.7 1028.08  4741.9 1030.11  4748.7 1026.94
  4769.4 1027.11  4800.4 1025.67  4817.0 1028.18  4822.2 1031.30  4831.5 1031.67
  4852.0 1029.53  4897.4 1028.90  4914.2 1027.63  4945.3 1027.69  4977.7 1026.32
  4990.8 1024.84  4991.3 1024.34  5001.1 1024.84  5021.2 1025.72  5039.7 1029.72
  5051.3 1029.72  5070.7 1031.79  5076.1 1031.34  5161.0 1034.61  5285.8 1040.38
#Mann=3,-1,0
  4603.8    0.05       0  4990.8    0.03       0  5001.1    0.05       0
Bank Sta=4990.8,5001.1
Exp/Cntr=0.3,0.1

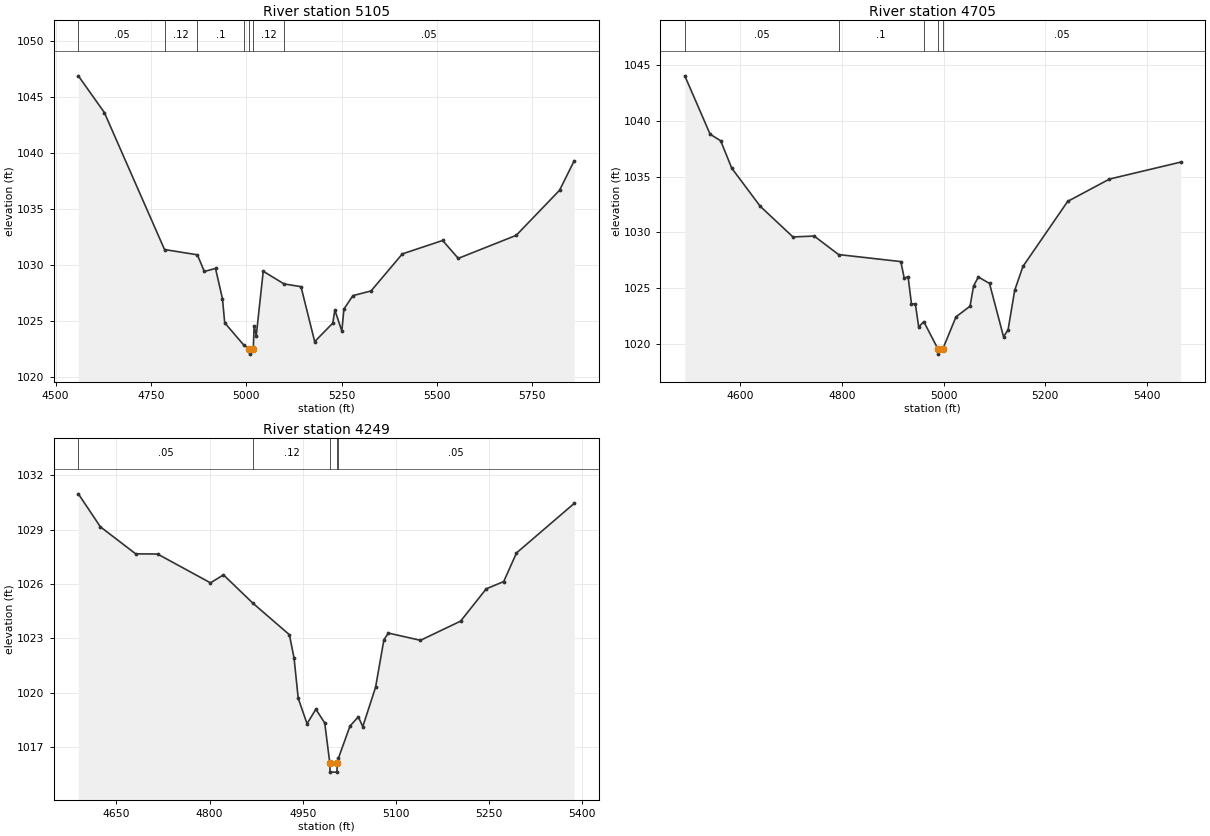
Type RM Length L Ch R = 1,5105,400,400,400
BEGIN DESCRIPTION:
BOARD BRANCH 10.0
END DESCRIPTION:
XS GIS Cut Line= 3
      2849455.67     10267803.15      2849289.50     10268211.00
      2848955.68     10269003.13
#Sta/Elev= 30
  4559.6 1046.89  4627.8 1043.61  4785.6 1031.36  4871.7 1030.89  4889.9 1029.40
  4919.3 1029.67  4937.5 1026.96  4943.4 1024.81  4994.1 1022.79  5008.0 1022.51
  5008.5 1022.01  5018.3 1022.51  5020.6 1024.55  5026.1 1023.67  5044.4 1029.42
  5098.8 1028.29  5143.4 1028.04  5179.3 1023.13  5226.7 1024.78  5232.2 1025.95
  5250.5 1024.07  5255.9 1026.04  5279.6 1027.24  5327.1 1027.66  5409.1 1030.97
  5514.8 1032.17  5555.7 1030.57  5707.7 1032.63  5821.3 1036.66  5859.6 1039.29
#Mann=7,-1,0
  4559.6    0.05       0  4785.6    0.12       0  4871.7     0.1       0
  4994.1    0.12       0  5008.0    0.07       0  5018.3    0.12       0
  5098.8    0.05       0
Bank Sta=5008,5018.3
Exp/Cntr=0.3,0.1

Type RM Length L Ch R = 1,4705,456,456,456
BEGIN DESCRIPTION:
BOARD BRANCH 9.0
END DESCRIPTION:
XS GIS Cut Line= 3
      2849355.70     10267703.10      2848974.50     10268041.00
      2848755.68     10268453.11
#Sta/Elev= 30
  4490.6 1044.03  4540.4 1038.80  4561.3 1038.20  4583.0 1035.75  4639.1 1032.33
  4703.5 1029.58  4745.3 1029.66  4793.3 1028.00  4915.9 1027.37  4922.6 1025.86
  4930.1 1026.03  4936.8 1023.57  4944.4 1023.58  4951.0 1021.51  4961.1 1021.98
  4988.5 1019.57  4989.0 1019.07  4998.8 1019.57  5024.4 1022.41  5052.1 1023.37
  5059.0 1025.18  5068.4 1025.99  5090.4 1025.41  5118.0 1020.63  5126.9 1021.24
  5140.0 1024.80  5156.3 1026.94  5244.3 1032.77  5326.5 1034.77  5466.6 1036.29
#Mann=5,-1,0
  4490.6    0.05       0  4793.3     0.1       0  4961.1    0.05       0
  4988.5    0.05       0  4998.8    0.05       0
Bank Sta=4988.5,4998.8
Exp/Cntr=0.3,0.1

Type RM Length L Ch R = 1,4249,458,458,458
BEGIN DESCRIPTION:
BOARD BRANCH 8.0
END DESCRIPTION:
XS GIS Cut Line= 3
      2848955.69     10267503.10      2848649.75     10267778.00
      2848555.69     10268153.09
#Sta/Elev= 30
  4588.7 1030.97  4624.2 1029.15  4681.0 1027.66  4716.2 1027.65  4801.4 1026.06
  4822.3 1026.50  4869.9 1024.93  4928.4 1023.20  4935.9 1021.91  4942.6 1019.69
  4956.8 1018.29  4971.0 1019.09  4985.3 1018.33  4993.4 1016.12  4993.9 1015.62
  5004.9 1015.62  5005.4 1016.12  5007.3 1016.39  5025.9 1018.16  5039.3 1018.67
  5046.5 1018.13  5067.1 1020.30  5080.5 1022.92  5087.7 1023.29  5139.3 1022.89
  5204.0 1023.95  5245.2 1025.73  5273.3 1026.13  5293.9 1027.71  5386.7 1030.44
#Mann=5,-1,0
  4588.7    0.05       0  4869.9    0.12       0  4993.4    0.07       0
  5005.4    0.12       0  5007.3    0.05       0
Bank Sta=4993.4,5005.4
Exp/Cntr=0.3,0.1