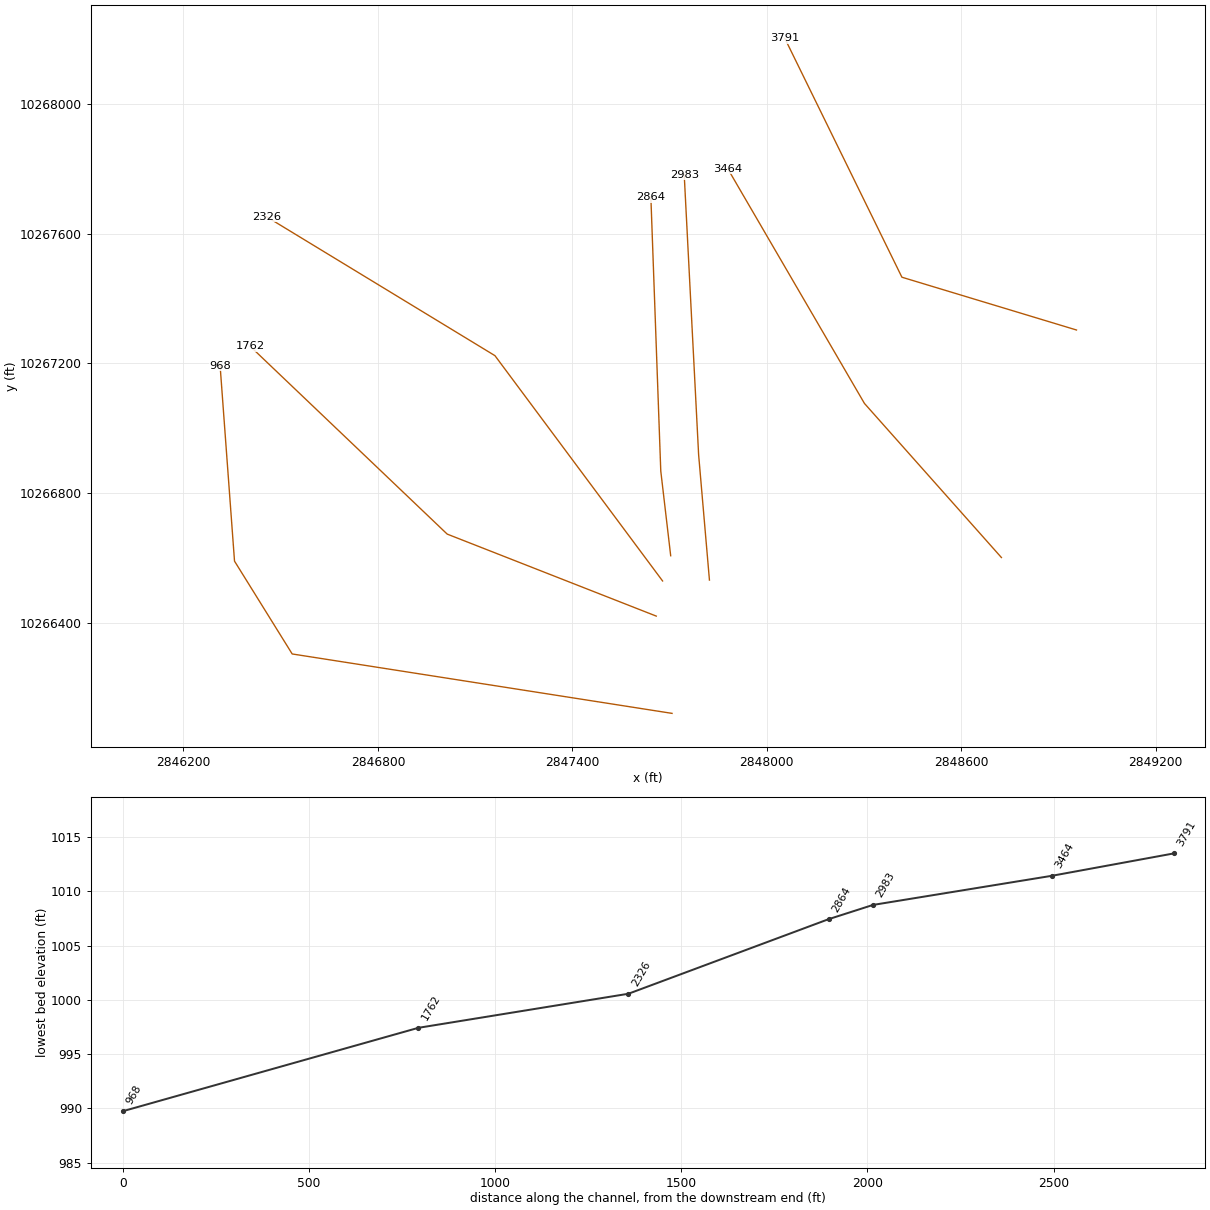
HEC-RAS study BOARD BRANCH.prj: BOARD BRANCH Base Level Engineering

--- BOARD BRANCH.g01 (geometry) --- (continued)

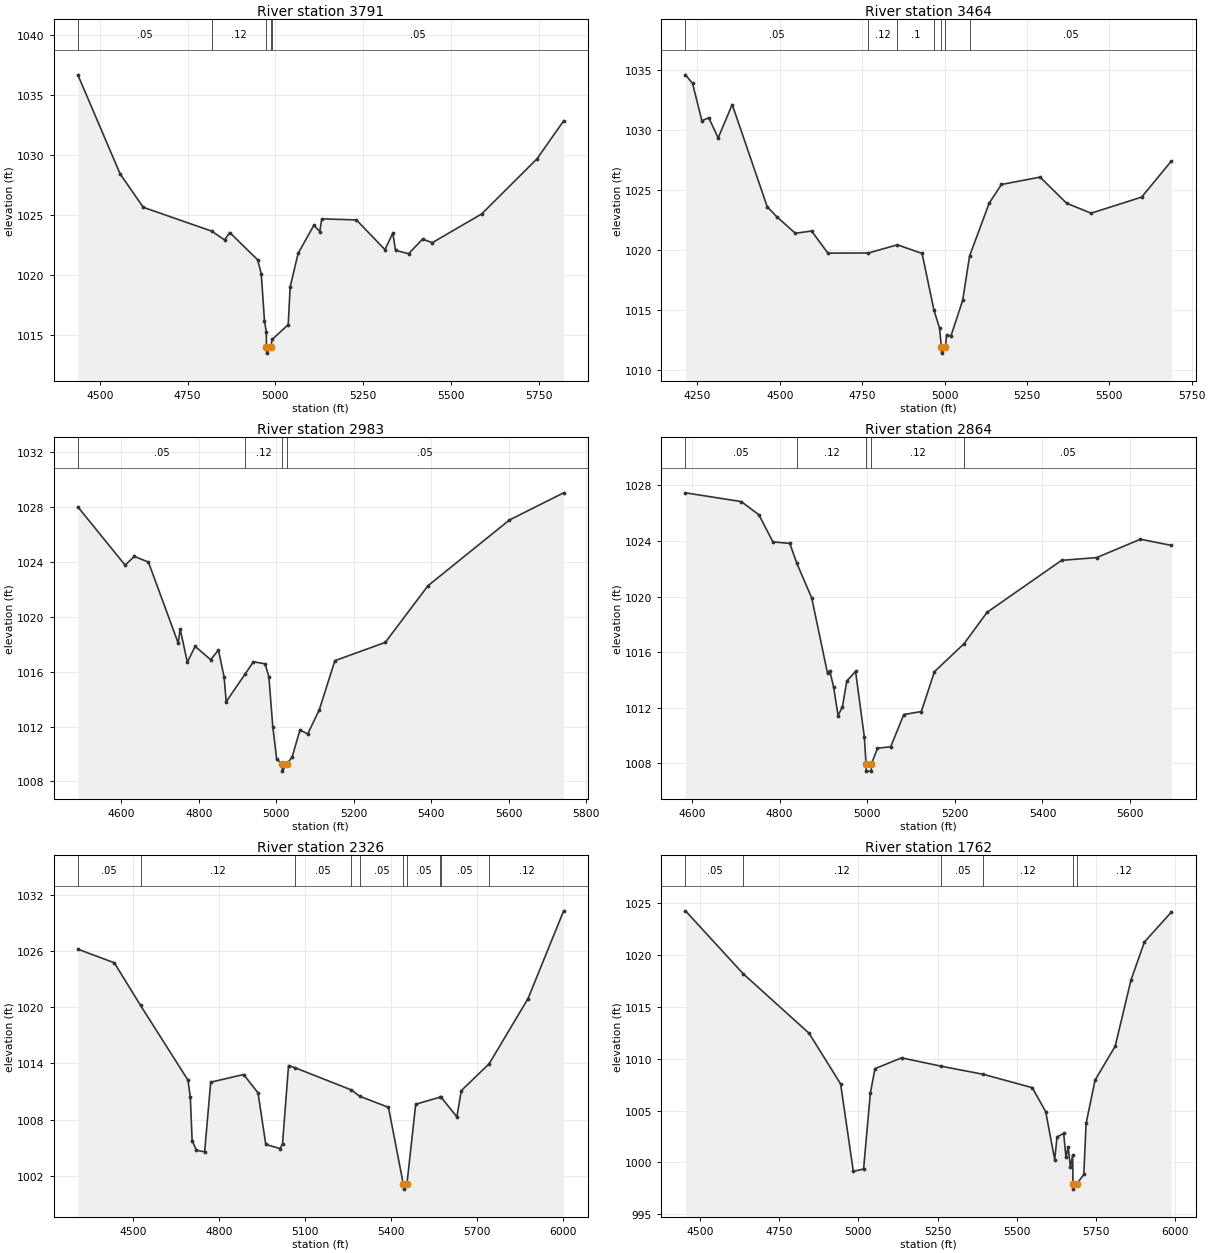
Type RM Length L Ch R = 1,3791,327,327,327
BEGIN DESCRIPTION:
BOARD BRANCH 7.0
END DESCRIPTION:
XS GIS Cut Line= 3
      2848955.71     10267303.10      2848417.00     10267466.00
      2848055.69     10268203.11
#Sta/Elev= 30
  4437.2 1036.65  4557.8 1028.40  4623.7 1025.63  4818.2 1023.65  4855.1 1022.92
  4869.9 1023.53  4949.1 1021.27  4959.6 1020.12  4968.8 1016.19  4974.0 1015.28
  4974.5 1014.00  4975.0 1013.50  4986.5 1014.00  4990.8 1014.64  5036.4 1015.87
  5042.0 1019.01  5064.5 1021.79  5109.5 1024.14  5126.4 1023.61  5132.0 1024.67
  5230.7 1024.58  5311.9 1022.11  5334.4 1023.49  5342.0 1022.05  5379.4 1021.77
  5418.9 1022.98  5446.9 1022.69  5587.5 1025.08  5744.9 1029.66  5820.9 1032.82
#Mann=5,-1,0
  4437.2    0.05       0  4818.2    0.12       0  4974.5    0.05       0
  4986.5    0.12       0  4990.8    0.05       0
Bank Sta=4974.5,4986.5
Exp/Cntr=0.3,0.1

Type RM Length L Ch R = 1,3464,481,481,481
BEGIN DESCRIPTION:
BOARD BRANCH 6.0
END DESCRIPTION:
XS GIS Cut Line= 3
      2848724.07     10266601.02      2848301.40     10267076.53
      2847879.68     10267800.67
#Sta/Elev= 30
  4213.9 1034.59  4235.4 1033.88  4263.8 1030.77  4284.7 1031.02  4313.2 1029.34
  4355.8 1032.12  4462.0 1023.62  4490.5 1022.80  4547.3 1021.41  4596.7 1021.60
  4646.0 1019.76  4769.1 1019.77  4856.9 1020.45  4932.0 1019.73  4967.9 1015.03
  4984.9 1013.52  4990.6 1011.94  4991.1 1011.44  5002.6 1011.94  5006.4 1012.93
  5019.7 1012.88  5055.2 1015.84  5076.1 1019.52  5135.5 1023.91  5172.7 1025.47
  5290.2 1026.08  5370.4 1023.91  5444.9 1023.08  5598.3 1024.42  5688.1 1027.41
#Mann=7,-1,0
  4213.9    0.05       0  4769.1    0.12       0  4856.9     0.1       0
  4967.9    0.12       0  4990.6    0.07       0  5002.6    0.12       0
  5076.1    0.05       0
Bank Sta=4990.6,5002.6
Exp/Cntr=0.3,0.1

Type RM Length L Ch R = 1,2983,119,119,119
BEGIN DESCRIPTION:
BOARD BRANCH 5.0
END DESCRIPTION:
XS GIS Cut Line= 3
      2847823.10     10266531.46      2847789.73     10266918.02
      2847745.23     10267782.88
#Sta/Elev= 30
  4487.4 1028.01  4609.5 1023.76  4633.2 1024.40  4669.7 1023.98  4746.5 1018.08
  4751.5 1019.11  4770.1 1016.69  4790.2 1017.84  4830.3 1016.87  4850.4 1017.57
  4864.9 1015.61  4870.4 1013.81  4919.8 1015.85  4940.6 1016.72  4970.6 1016.57
  4980.6 1015.62  4990.6 1011.99  5000.7 1009.62  5014.7 1009.25  5015.2 1008.75
  5026.7 1009.25  5040.7 1009.79  5060.7 1011.75  5080.8 1011.46  5110.8 1013.23
  5150.9 1016.80  5281.0 1018.13  5391.2 1022.26  5601.4 1027.05  5741.4 1029.03
#Mann=4,-1,0
  4487.4    0.05       0  4919.8    0.12       0  5014.7    0.07       0
  5026.7    0.05       0
Bank Sta=5014.7,5026.7
Exp/Cntr=0.3,0.1

Type RM Length L Ch R = 1,2864,538,538,538
BEGIN DESCRIPTION:
BOARD BRANCH 4.0
END DESCRIPTION:
XS GIS Cut Line= 3
      2847703.52     10266606.57      2847672.93     10266867.97
      2847642.34     10267713.33
#Sta/Elev= 30
  4584.9 1027.47  4712.3 1026.84  4752.6 1025.89  4784.6 1023.94  4823.1 1023.83
  4839.3 1022.39  4873.2 1019.90  4909.3 1014.48  4914.3 1014.68  4923.3 1013.47
  4933.3 1011.44  4943.3 1012.07  4953.3 1013.93  4973.3 1014.62  4993.3 1009.90
  4997.2 1007.94  4997.7 1007.44  5008.9 1007.44  5009.4 1007.94  5023.3 1009.09
  5053.4 1009.19  5083.4 1011.51  5123.4 1011.73  5153.4 1014.60  5220.9 1016.61
  5273.5 1018.87  5443.6 1022.61  5523.7 1022.81  5623.7 1024.13  5694.0 1023.69
#Mann=5,-1,0
  4584.9    0.05       0  4839.3    0.12       0  4997.2    0.07       0
  5009.4    0.12       0  5220.9    0.05       0
Bank Sta=4997.2,5009.4
Exp/Cntr=0.3,0.1

Type RM Length L Ch R = 1,2326,564,564,564
BEGIN DESCRIPTION:
BOARD BRANCH 3.0
END DESCRIPTION:
XS GIS Cut Line= 3
      2847678.49     10266528.71      2847161.26     10267223.91
      2846455.66     10267653.13
#Sta/Elev= 30
  4308.7 1026.23  4435.8 1024.77  4527.2 1020.21  4692.3 1012.22  4700.6 1010.39
  4706.9 1005.75  4721.6 1004.72  4750.4 1004.55  4771.6 1012.00  4886.3 1012.82
  4936.4 1010.86  4963.5 1005.34  5013.5 1004.90  5021.9 1005.44  5042.7 1013.78
  5064.2 1013.56  5261.4 1011.17  5291.0 1010.49  5390.8 1009.31  5442.8 1001.06
  5443.3 1000.56  5455.0 1001.06  5485.7 1009.64  5570.8 1010.40  5574.8 1010.37
  5629.1 1008.29  5644.6 1011.10  5741.6 1013.97  5877.1 1020.95  6001.1 1030.33
#Mann=10,-1,0
  4308.7    0.05       0  4527.2    0.12       0  5064.2    0.05       0
  5261.4    0.12       0  5291.0    0.05       0  5442.8    0.07       0
  5455.0    0.05       0  5570.8    0.12       0  5574.8    0.05       0
  5741.6    0.12       0
Bank Sta=5442.8,5455
Exp/Cntr=0.3,0.1

Type RM Length L Ch R = 1,1762,794,794,794
BEGIN DESCRIPTION:
BOARD BRANCH 2.0
END DESCRIPTION:
XS GIS Cut Line= 3
      2847659.03     10266420.26      2847013.88     10266673.31
      2846405.67     10267253.12
#Sta/Elev= 30
  4454.4 1024.28  4636.9 1018.20  4844.7 1012.46  4944.1 1007.57  4984.3  999.13
  5016.6  999.36  5038.0 1006.69  5052.6 1009.05  5136.6 1010.09  5262.1 1009.28
  5394.5 1008.50  5549.1 1007.21  5591.5 1004.89  5619.8 1000.26  5627.1 1002.45
  5648.1 1002.80  5655.4 1000.49  5662.3 1001.47  5669.6  999.52  5676.5 1000.71
  5677.6  997.92  5678.1  997.42  5689.8  997.92  5711.7  998.85  5718.9 1003.76
  5747.2 1007.94  5810.8 1011.22  5860.5 1017.59  5902.9 1021.27  5987.7 1024.15
#Mann=6,-1,0
  4454.4    0.05       0  4636.9    0.12       0  5262.1    0.05       0
  5394.5    0.12       0  5677.6    0.07       0  5689.8    0.12       0
Bank Sta=5677.6,5689.8
Exp/Cntr=0.3,0.1

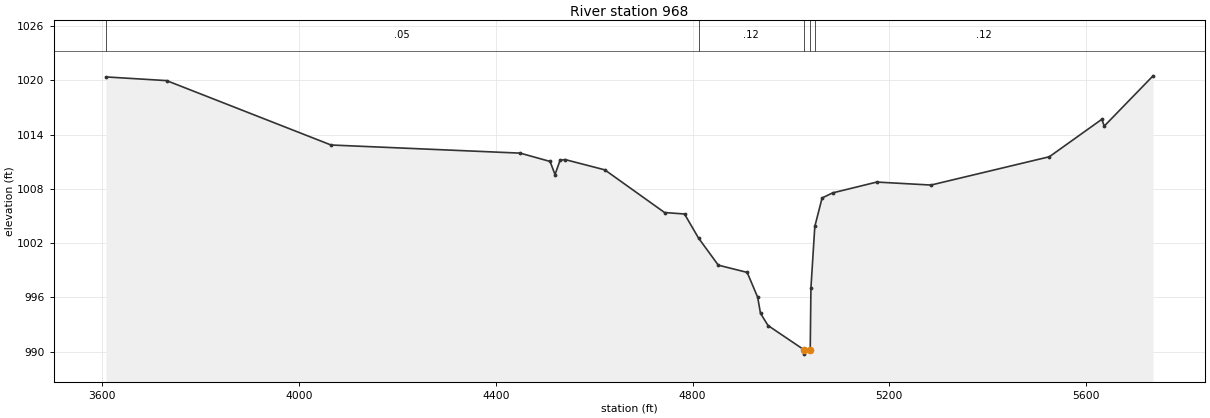
Type RM Length L Ch R = 1,968,0,0,0
BEGIN DESCRIPTION:
BOARD BRANCH 1.0
END DESCRIPTION:
XS GIS Cut Line= 4
      2847707.75     10266120.11      2846535.58     10266303.46
      2846357.61     10266589.89      2846313.11     10267193.32
#Sta/Elev= 30
  3607.5 1020.39  3731.0 1019.98  4065.1 1012.86  4449.7 1011.96  4510.4 1011.04
  4520.5 1009.59  4530.7 1011.16  4540.8 1011.25  4621.7 1010.11  4743.2 1005.39
  4783.7 1005.23  4812.2 1002.57  4852.4  999.57  4911.1  998.77  4932.4  996.03
  4938.2  994.24  4953.6  992.89  5026.1  990.23  5026.6  989.73  5039.3  990.23
  5040.7  997.03  5048.6 1003.85  5063.4 1007.00  5084.7 1007.56  5174.5 1008.76
  5284.8 1008.43  5525.4 1011.56  5632.0 1015.70  5637.0 1014.95  5736.2 1020.51
#Mann=5,-1,0
  3607.5    0.05       0  4812.2    0.12       0  5026.1    0.07       0
  5039.3    0.12       0  5048.6    0.12       0
Bank Sta=5026.1,5039.3
Exp/Cntr=0.3,0.1

Chan Stop Cuts=-1