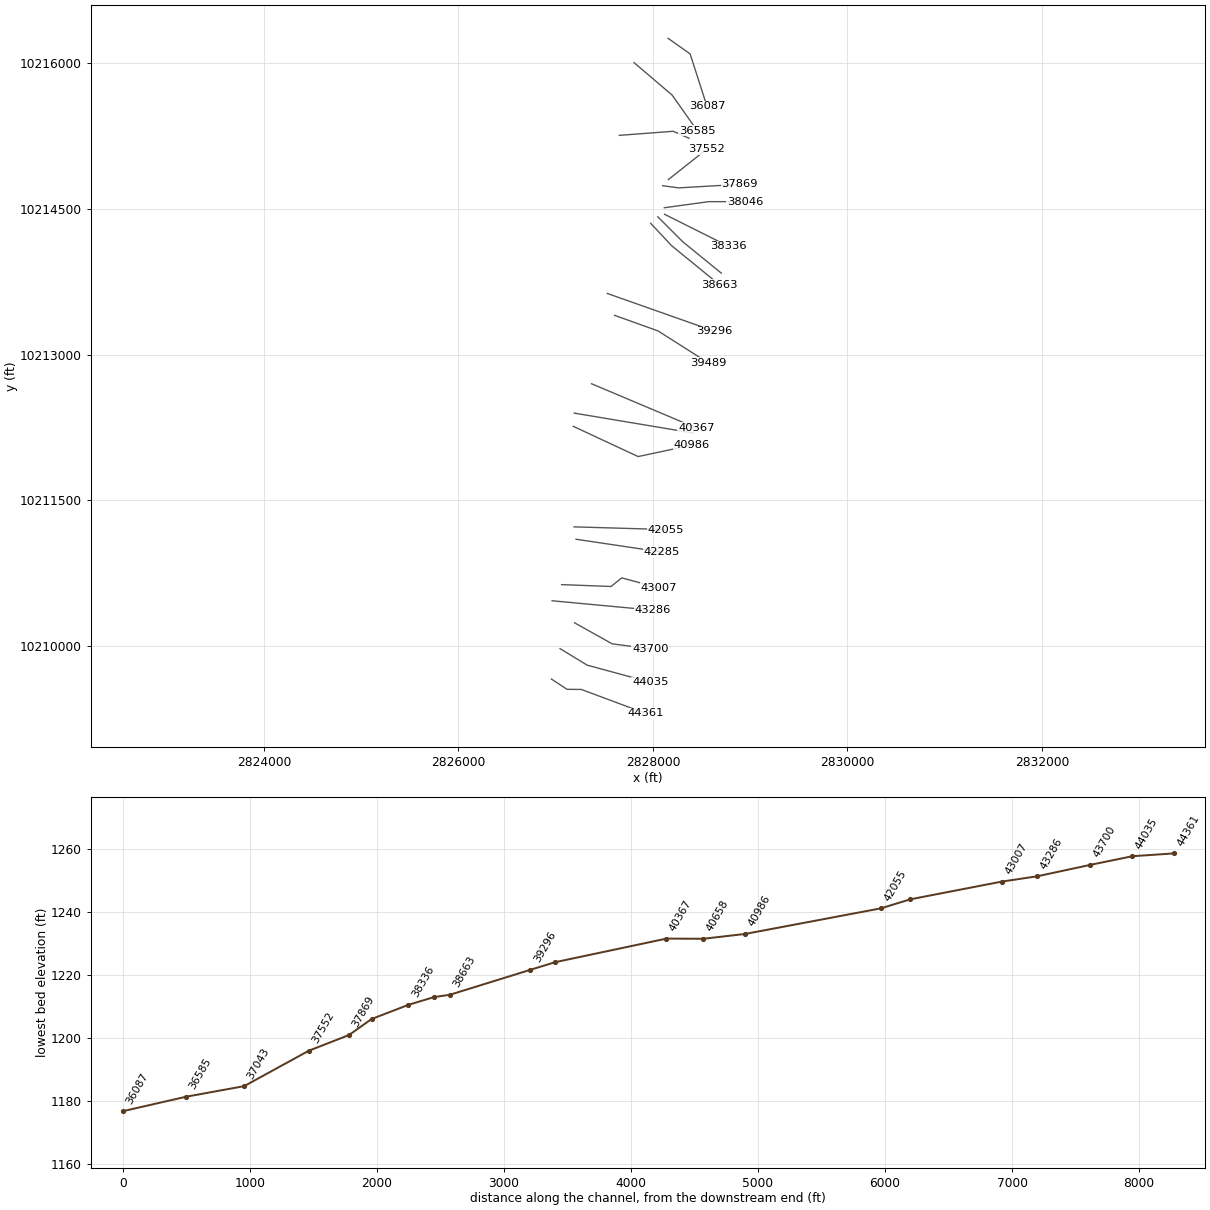
HEC-RAS study BYRNES CREEK.prj: BYRNES CREEK Base Level Engineering

--- BYRNES CREEK.g01 (geometry) --- (continued)

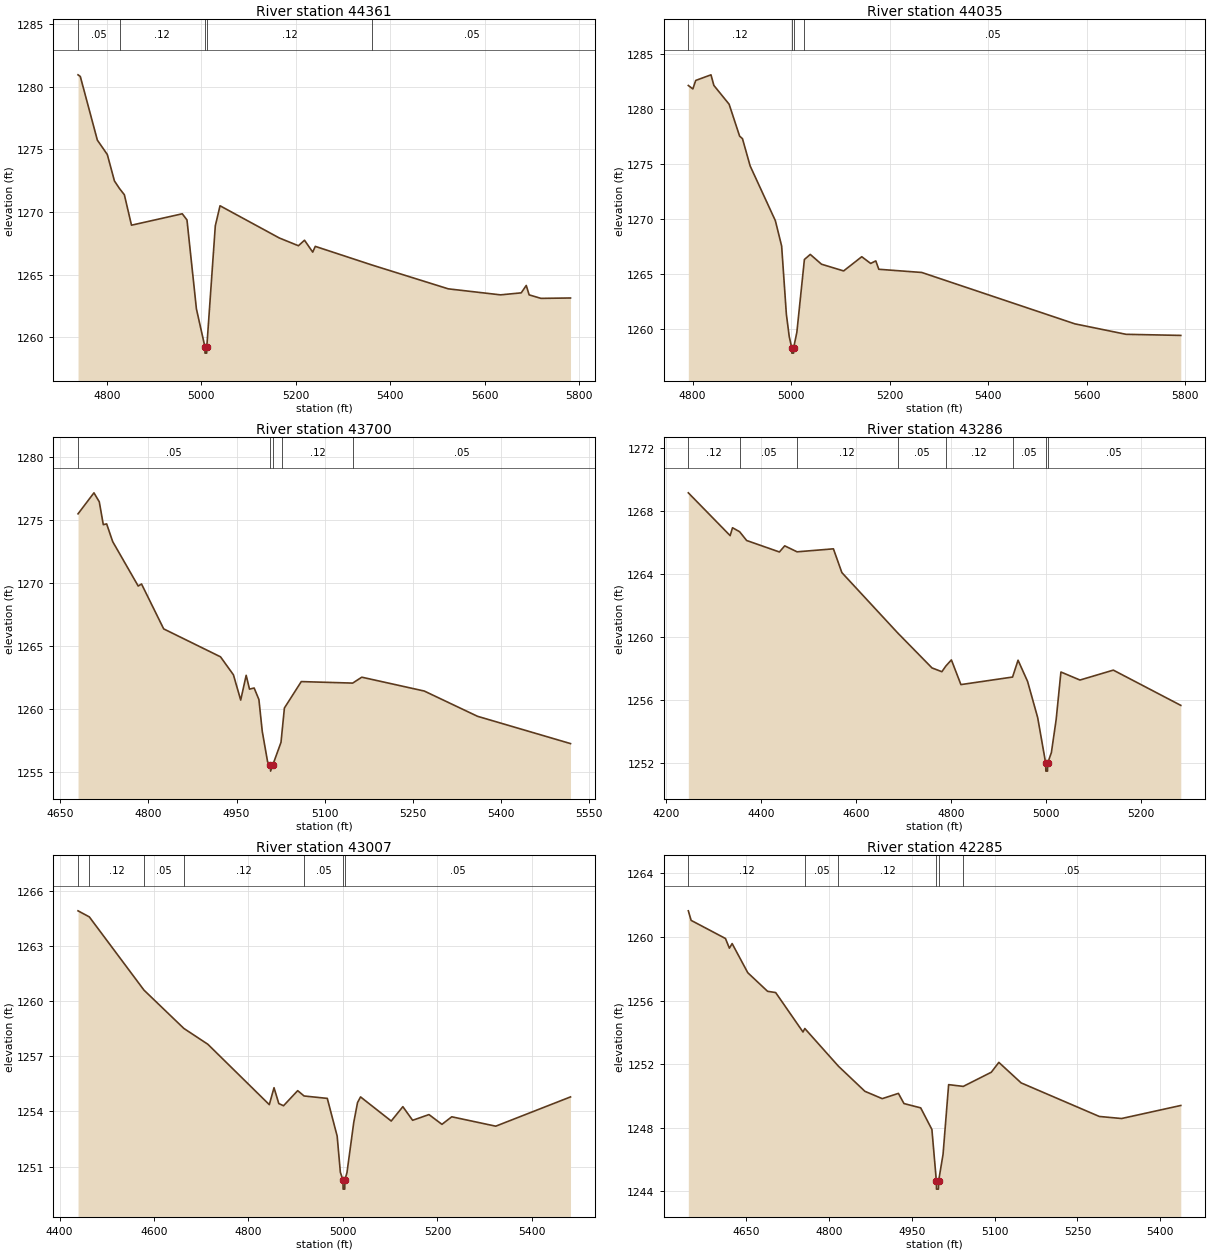
Type RM Length L Ch R = 1 ,44361   ,326,326,326
BEGIN DESCRIPTION:
BYRNES CREEK 78.0
END DESCRIPTION:
XS GIS Cut Line= 4
      2826956.63     10209660.69       2827116.8     10209555.21
      2827263.94      10209553.9      2827923.47     10209307.75
#Sta/Elev= 30
  4738.9 1280.94  4743.7 1280.81  4779.8 1275.73  4800.9 1274.58    4816 1272.47
  4826.8 1271.86    4837 1271.37  4852.1 1268.94  4959.6 1269.85  4969.6 1269.36
  4989.6 1262.26  5007.6 1259.23  5007.8 1258.73  5011.3 1258.73  5011.6 1259.23
  5029.6 1268.89  5039.6 1270.49  5165.1 1267.92  5205.6  1267.3  5218.5 1267.74
  5235.9 1266.79  5241.3 1267.25  5362.4 1265.75    5523 1263.86  5633.6 1263.38
  5677.4 1263.54  5688.1 1264.13  5694.2 1263.38  5719.2  1263.1  5781.8 1263.13
#Mann= 5 ,-1 , 0
  4738.9     .05       0  4826.8     .12       0  5007.6     .07       0
  5011.6     .12       0  5362.4     .05       0
Bank Sta=5007.6,5011.6
XS Rating Curve= 0 ,0
Exp/Cntr=0.3,0.1

Type RM Length L Ch R = 1 ,44035   ,335,335,335
BEGIN DESCRIPTION:
Mapping XS 4998bb02
END DESCRIPTION:
XS GIS Cut Line= 3
      2827044.75     10209974.04      2827324.27      10209803.9
      2827973.03     10209627.66
#Sta/Elev= 30
  4791.5 1282.16  4800.7 1281.85  4806.5 1282.62  4837.5 1283.13  4843.3 1282.17
  4874.3 1280.46  4895.6 1277.56  4901.4 1277.33  4916.9 1274.86  4968.2 1269.87
  4980.9 1267.57  4990.5 1261.37  4996.3 1259.35  5001.3 1258.34  5001.6 1257.84
  5005.1 1257.84  5005.3 1258.34  5011.8 1259.74  5027.1 1266.35    5039 1266.81
  5061.8 1265.92  5106.7 1265.31  5143.5  1266.6  5161.6 1265.99    5172 1266.22
  5178.1 1265.46  5265.3 1265.17  5576.1  1260.5  5679.9 1259.55    5791 1259.45
#Mann= 4 ,-1 , 0
  4791.5     .12       0  5001.3     .07       0  5005.3     .12       0
  5027.1     .05       0
Bank Sta=5001.3,5005.3
XS Rating Curve= 0 ,0
Exp/Cntr=0.3,0.1

Type RM Length L Ch R = 1 ,43700   ,414,414,414
BEGIN DESCRIPTION:
Mapping XS 561c4de4
END DESCRIPTION:
XS GIS Cut Line= 3
      2827194.09     10210239.65      2827580.65     10210023.25
       2827972.6     10209972.01
#Sta/Elev= 30
  4680.2 1275.52  4707.3 1277.19  4716.4 1276.47  4723.2 1274.66  4728.9 1274.72
  4739.2 1273.31  4782.6 1269.78  4788.3 1269.94    4826 1266.37  4922.7 1264.15
  4944.7 1262.72  4957.1 1260.71  4966.4 1262.68  4972.1 1261.58    4980 1261.67
  4988.1 1260.75  4993.8 1258.22  5002.9  1255.8  5007.8 1255.56    5008 1255.06
  5011.8 1255.56  5025.7 1257.35  5027.9 1258.39  5031.5 1260.08  5060.2 1262.18
  5147.7 1262.06  5163.2 1262.53  5269.5 1261.43  5360.2 1259.42  5518.5 1257.25
#Mann= 5 ,-1 , 0
  4680.2     .05       0  5007.8     .05       0  5011.8     .05       0
  5027.9     .12       0  5147.7     .05       0
Bank Sta=5007.8,5011.8
XS Rating Curve= 0 ,0
Exp/Cntr=0.3,0.1

Type RM Length L Ch R = 1 ,43286   ,279,279,279
BEGIN DESCRIPTION:
Mapping XS 27461ba5
END DESCRIPTION:
XS GIS Cut Line= 2
      2826963.26     10210466.35      2827997.35     10210369.66
#Sta/Elev= 30
  4246.1 1269.16  4334.3 1266.44  4339.3 1266.94  4354.2 1266.69  4369.1 1266.13
  4438.2  1265.4  4449.4 1265.79  4475.4 1265.41  4552.1  1265.6  4569.9 1264.09
  4687.5 1260.26    4760 1258.03  4780.8 1257.79  4789.2 1258.15  4800.9 1258.54
    4821 1256.97  4929.9 1257.45  4941.5 1258.52  4961.6 1257.17  4982.9 1254.87
  4999.8 1251.97  5000.1 1251.47  5003.6 1251.47  5003.8 1251.97  5011.8 1252.65
  5021.9 1254.76  5031.9 1257.77  5072.1 1257.26  5142.4 1257.89  5284.7 1255.65
#Mann= 8 ,-1 , 0
  4246.1     .12       0  4354.2     .05       0  4475.4     .12       0
  4687.5     .05       0  4789.2     .12       0  4929.9     .05       0
  4999.8     .05       0  5003.8     .05       0
Bank Sta=4999.8,5003.8
XS Rating Curve= 0 ,0
Exp/Cntr=0.3,0.1

Type RM Length L Ch R = 1 ,43007   ,722,722,722
BEGIN DESCRIPTION:
Mapping XS 896c8bc9
END DESCRIPTION:
XS GIS Cut Line= 4
      2827060.93     10210632.51      2827569.59     10210613.41
      2827678.97     10210701.95      2828058.53     10210599.83
#Sta/Elev= 30
  4439.1  1264.9    4463 1264.57  4578.8 1260.59  4663.2 1258.51    4714 1257.65
  4844.1 1254.37  4854.1 1255.29  4864.2 1254.43  4874.2 1254.31  4904.2 1255.13
  4917.8 1254.84  4966.9 1254.71  4987.8 1252.66  4994.6 1250.69  5000.1 1250.28
  5000.4 1249.78  5003.9 1249.78  5004.1 1250.28  5008.6 1250.68  5022.9  1253.4
  5030.9 1254.48  5037.3 1254.79  5102.3 1253.48  5126.9 1254.26  5147.6 1253.52
  5182.2 1253.83  5209.7  1253.3  5230.4 1253.71  5323.6  1253.2  5481.9 1254.79
#Mann= 7 ,-1 , 0
  4439.1     .05       0    4463     .12       0  4578.8     .05       0
  4663.2     .12       0  4917.8     .05       0  5000.1     .05       0
  5004.1     .05       0
Bank Sta=5000.1,5004.1
XS Rating Curve= 0 ,0
Exp/Cntr=0.3,0.1

Type RM Length L Ch R = 1 ,42285   ,230,230,230
BEGIN DESCRIPTION:
Mapping XS 9f9ba7a5
END DESCRIPTION:
XS GIS Cut Line= 2
      2827209.15      10211099.4      2828091.77     10210967.61
#Sta/Elev= 30
  4544.9 1261.64    4550 1261.04  4612.2  1259.9  4619.3 1259.29  4624.3 1259.58
  4652.6 1257.75  4688.5 1256.58  4703.2  1256.5  4752.7 1254.02    4756 1254.24
  4816.9 1251.87  4864.9 1250.29  4896.3 1249.83  4925.6 1250.16  4935.7 1249.52
    4966 1249.25  4986.3 1247.89  4994.4 1244.64  4994.6 1244.14  4998.1 1244.14
  4998.4 1244.64  5006.5 1246.33  5016.6 1250.71  5043.1  1250.6  5093.9 1251.49
  5107.6 1252.11    5148 1250.82  5289.6 1248.71    5330 1248.58  5437.3  1249.4
#Mann= 6 ,-1 , 0
  4544.9     .12       0    4756     .05       0  4816.9     .12       0
  4994.4     .07       0  4998.4     .12       0  5043.1     .05       0
Bank Sta=4994.4,4998.4
XS Rating Curve= 0 ,0
Exp/Cntr=0.3,0.1

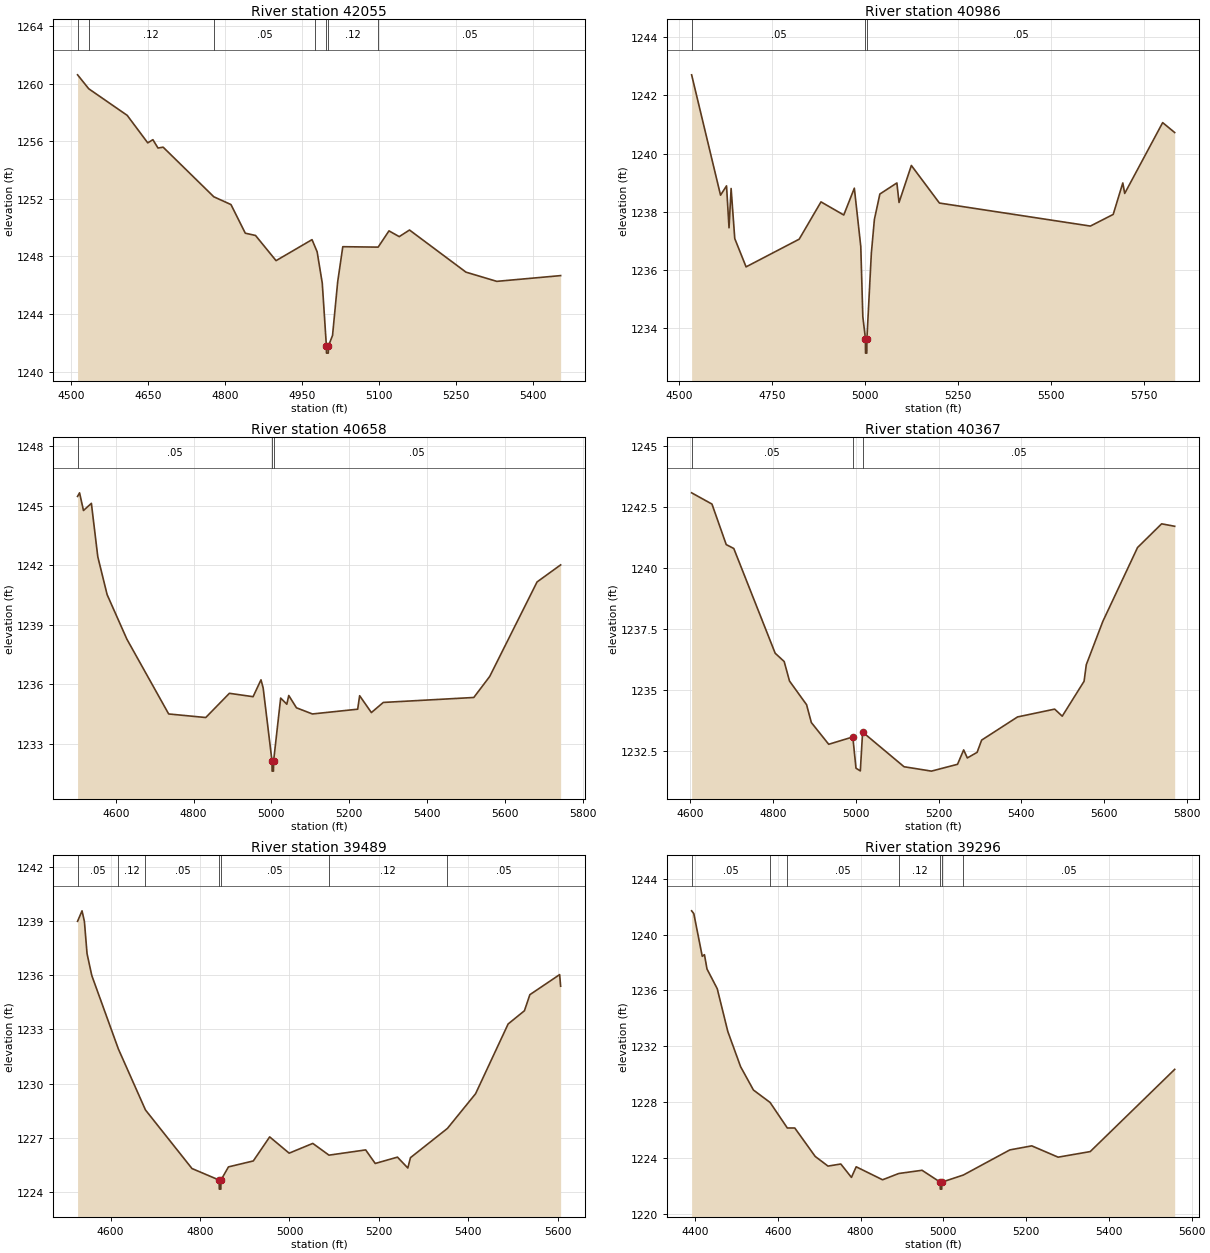
Type RM Length L Ch R = 1 ,42055   ,1069,1069,1069
BEGIN DESCRIPTION:
Mapping XS 05b76a36
END DESCRIPTION:
XS GIS Cut Line= 2
      2827188.91     10211226.77      2828130.11     10211199.23
#Sta/Elev= 30
  4512.5 1260.63  4534.3 1259.66  4609.3 1257.81  4649.3  1255.9  4659.3 1256.12
  4669.3 1255.54  4679.3  1255.6  4778.1 1252.15  4811.5 1251.61  4839.4 1249.62
  4859.4 1249.46  4899.4 1247.71  4969.5 1249.17  4975.9 1248.63  4979.5 1248.32
  4989.5 1246.14  4997.5 1241.78  4997.7 1241.28  5001.2 1241.28  5001.5 1241.78
  5009.5 1242.51  5019.5 1246.23  5029.5 1248.68  5098.4 1248.65  5119.5 1249.78
  5139.5 1249.38  5159.5 1249.84  5269.6 1246.91  5329.6 1246.27  5454.1 1246.67
#Mann= 7 ,-1 , 0
  4512.5     .05       0  4534.3     .12       0  4778.1     .05       0
  4975.9     .12       0  4997.5     .07       0  5001.5     .12       0
  5098.4     .05       0
Bank Sta=4997.5,5001.5
XS Rating Curve= 0 ,0
Exp/Cntr=0.3,0.1

Type RM Length L Ch R = 1 ,40986   ,328,328,328
BEGIN DESCRIPTION:
Mapping XS e2ab347d
END DESCRIPTION:
XS GIS Cut Line= 3
      2827180.65     10212261.11      2827847.56     10211950.05
      2828397.25     10212067.08
#Sta/Elev= 30
  4533.7  1242.7  4611.4 1238.57  4627.5 1238.89  4634.2 1237.45  4639.8  1238.8
  4649.6 1237.08    4680 1236.11  4822.7 1237.06  4881.3 1238.34  4942.5 1237.89
  4970.9 1238.81  4988.2 1236.81  4993.7  1234.4  5000.7 1233.65  5000.9 1233.15
  5004.4 1233.15  5004.7 1233.65  5016.6 1236.58  5024.8 1237.74  5039.5 1238.61
  5085.2 1238.99    5091 1238.32  5124.1 1239.59  5199.5  1238.3  5605.1 1237.51
  5666.4 1237.91  5692.2 1238.99  5697.3 1238.63  5799.3 1241.06  5831.6 1240.72
#Mann= 3 ,-1 , 0
  4533.7     .05       0  5000.7     .05       0  5004.7     .05       0
Bank Sta=5000.7,5004.7
XS Rating Curve= 0 ,0
Exp/Cntr=0.3,0.1

Type RM Length L Ch R = 1 ,40658   ,291,291,291
BEGIN DESCRIPTION:
Mapping XS 87b49412
END DESCRIPTION:
XS GIS Cut Line= 2
      2827190.69     10212396.91      2828415.48     10212192.09
#Sta/Elev= 30
  4501.9 1245.46    4507 1245.64  4517.1 1244.75  4537.4 1245.11  4553.9 1242.42
  4577.9 1240.51  4628.6 1238.27  4736.1  1234.5  4831.4 1234.32  4892.2 1235.54
  4953.1 1235.37  4973.4 1236.22    4979 1235.81  5001.8 1232.12    5002 1231.62
  5005.5 1231.62  5005.8 1232.12    5024  1235.3  5039.8 1234.99  5044.8 1235.43
  5064.6 1234.81  5105.6  1234.5    5222 1234.74    5227 1235.42  5257.2 1234.57
  5287.8 1235.08  5520.5 1235.33  5561.4 1236.39  5683.1 1241.15  5743.7 1242.01
#Mann= 3 ,-1 , 0
  4501.9     .05       0  5001.8     .05       0  5005.8     .05       0
Bank Sta=5001.8,5005.8
XS Rating Curve= 0 ,0
Exp/Cntr=0.3,0.1

Type RM Length L Ch R = 1 ,40367   ,878,878,878
BEGIN DESCRIPTION:
Mapping XS 8da22d8f
END DESCRIPTION:
XS GIS Cut Line= 2
      2827369.49     10212698.99      2828445.83     10212244.15
#Sta/Elev= 30
  4602.8 1243.07    4652 1242.61  4686.5 1240.95  4704.8 1240.79  4804.9  1236.5
  4826.7 1236.16  4839.6 1235.36  4880.9 1234.39  4892.4 1233.66  4934.4 1232.77
  4992.7 1233.07  5000.4 1231.79  5010.9 1231.68  5016.4 1233.27  5116.6 1231.85
  5182.9 1231.67    5246 1231.95  5260.9 1232.54  5269.7 1232.21  5293.4 1232.44
  5304.3 1232.94  5391.2 1233.89    5481 1234.21  5499.3 1233.92  5552.1 1235.35
  5557.5 1236.03  5597.4  1237.8  5681.5 1240.83  5739.7  1241.8  5771.3  1241.7
#Mann= 3 ,-1 , 0
  4602.8     .05       0  4992.7     .05       0  5016.4     .05       0
Bank Sta=4992.7,5016.4
XS Rating Curve= 0 ,0
Exp/Cntr=0.3,0.1

Type RM Length L Ch R = 1 ,39489   ,193,193,193
BEGIN DESCRIPTION:
BYRNES CREEK 71.0
END DESCRIPTION:
XS GIS Cut Line= 3
      2827605.71      10213403.1      2828051.75       10213243.
      2828563.74     10212917.68
#Sta/Elev= 30
  4526.1 1238.98  4536.1 1239.56  4541.4 1238.97  4547.3 1237.19  4557.9 1235.98
  4617.3 1231.92    4678 1228.54    4782  1225.3  4842.8 1224.66  4843.1 1224.16
  4846.6 1224.16  4846.8 1224.66  4863.6 1225.39  4919.2 1225.72  4955.8 1227.05
  4999.4 1226.15  5052.2 1226.69  5088.5 1226.04  5170.5 1226.33  5191.9 1225.58
  5241.6 1225.93  5264.8 1225.33  5270.7  1225.9  5353.4 1227.52  5416.4 1229.44
  5489.2  1233.3  5525.6 1234.03  5537.8 1234.92  5604.4 1236.03  5606.6 1235.39
#Mann= 7 ,-1 , 0
  4526.1     .05       0  4617.3     .12       0    4678     .05       0
  4842.8     .05       0  4846.8     .05       0  5088.5     .12       0
  5353.4     .05       0
Bank Sta=4842.8,4846.8
XS Rating Curve= 0 ,0
Exp/Cntr=0.3,0.1

Type RM Length L Ch R = 1 ,39296   ,633,633,633
BEGIN DESCRIPTION:
Mapping XS 7b8d9e2a
END DESCRIPTION:
XS GIS Cut Line= 2
      2827530.64     10213628.13      2828631.35      10213239.5
#Sta/Elev= 30
  4391.7  1241.7    4397  1241.5  4417.4 1238.44  4422.7 1238.56  4428.9 1237.53
  4453.6 1236.12  4479.2 1233.05  4510.1 1230.53  4541.1 1228.86  4581.3 1227.97
    4623 1226.14    4641 1226.14  4690.4  1224.1  4721.3 1223.41  4752.2 1223.56
  4777.9  1222.6  4789.4 1223.36  4853.1 1222.43  4892.3 1222.88  4948.5 1223.11
  4992.4 1222.26  4992.6 1221.76  4996.1 1221.76  4996.4 1222.26  5048.3 1222.77
  5160.6 1224.57  5213.6 1224.86  5277.3 1224.05  5354.9 1224.45    5559 1230.34
#Mann= 7 ,-1 , 0
  4391.7     .05       0  4581.3     .12       0    4623     .05       0
  4892.3     .12       0  4992.4     .07       0  4996.4     .12       0
  5048.3     .05       0
Bank Sta=4992.4,4996.4
XS Rating Curve= 0 ,0
Exp/Cntr=0.3,0.1

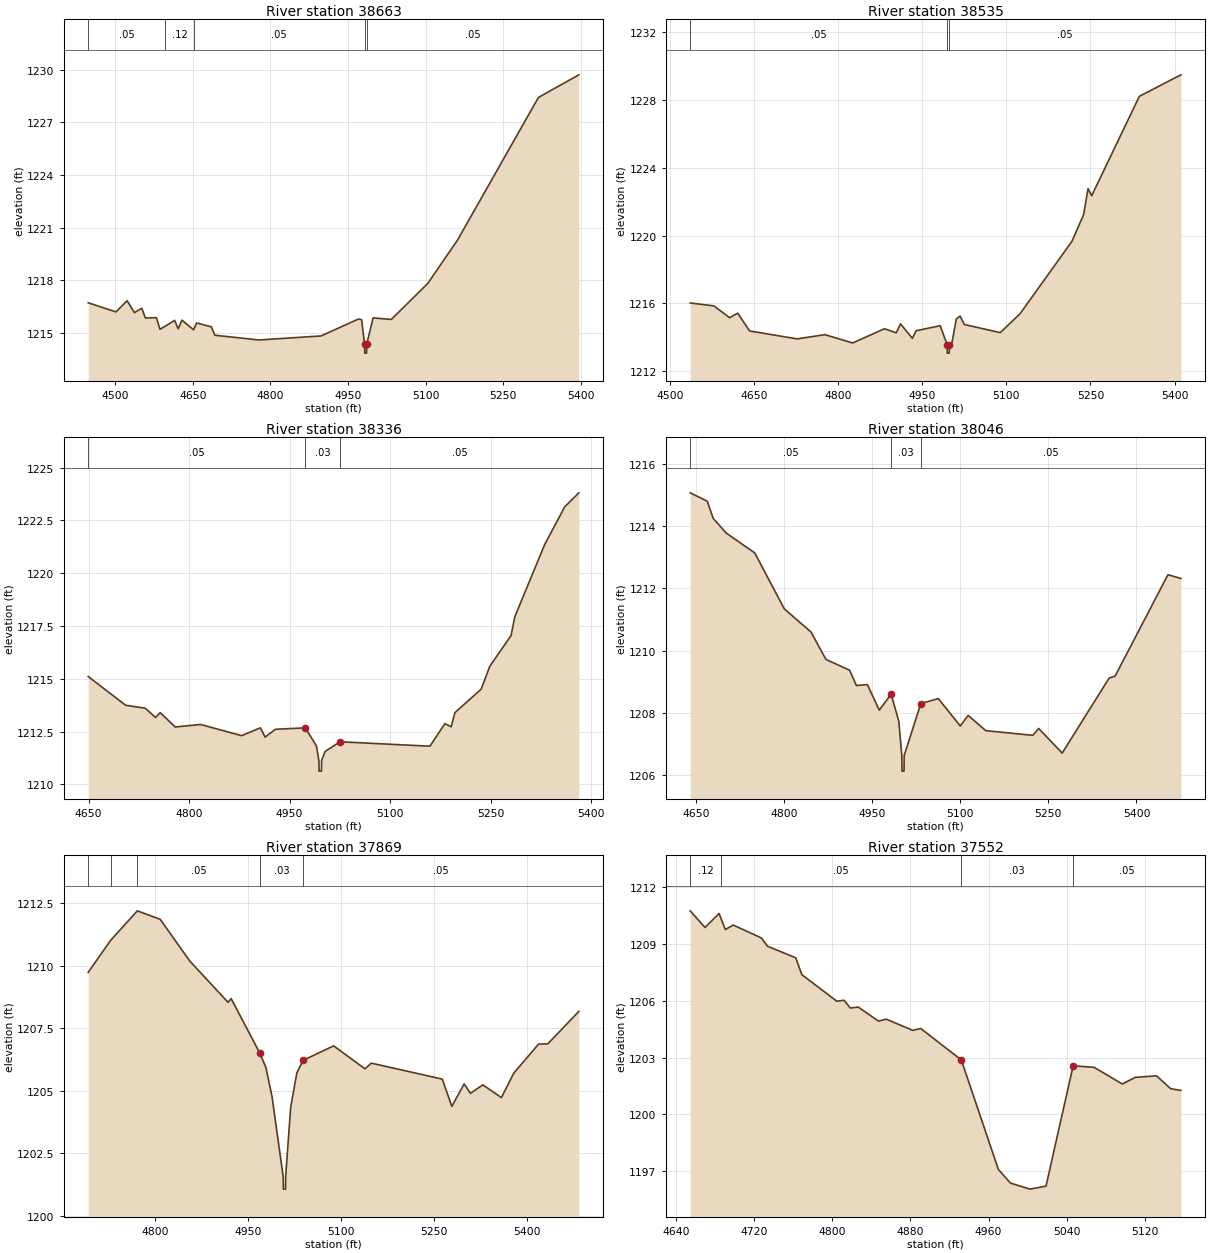
Type RM Length L Ch R = 1 ,38663   ,128,128,128
BEGIN DESCRIPTION:
Mapping XS ebd20b06
END DESCRIPTION:
XS GIS Cut Line= 3
      2827976.54     10214350.03      2828192.11     10214119.37
      2828682.21     10213719.56
#Sta/Elev= 30
    4448 1216.71  4501.7 1216.19  4523.2 1216.83  4537.3 1216.15  4551.5  1216.4
  4558.4 1215.85  4579.8 1215.86  4586.7  1215.2  4597.1 1215.38    4615 1215.71
  4621.9 1215.23  4629.2 1215.72  4651.7 1215.17  4657.5 1215.56  4685.9 1215.34
  4692.7 1214.86  4778.1 1214.59    4898 1214.82  4969.9 1215.78  4976.3 1215.75
  4982.2 1214.34  4982.5 1213.84    4986 1213.84  4986.2 1214.34  4998.6 1215.85
  5033.8 1215.76  5104.1 1217.81  5161.6 1220.28  5318.1 1228.42  5396.2 1229.71
#Mann= 5 ,-1 , 0
    4448     .05       0  4597.1     .12       0  4651.7     .05       0
  4982.2     .05       0  4986.2     .05       0
Bank Sta=4982.2,4986.2
XS Rating Curve= 0 ,0
Exp/Cntr=0.3,0.1

Type RM Length L Ch R = 1 ,38535   ,199,199,199
BEGIN DESCRIPTION:
Mapping XS 1116d0ab
END DESCRIPTION:
XS GIS Cut Line= 3
      2828049.84     10214416.86      2828306.37     10214160.34
      2828703.07     10213836.94
#Sta/Elev= 30
  4536.6 1216.03  4578.7 1215.86    4607 1215.16  4621.2 1215.43  4642.4 1214.38
  4727.2 1213.91  4776.7 1214.16  4826.2 1213.67  4882.8 1214.51  4903.9 1214.27
  4911.4  1214.8  4932.7 1213.94  4939.1 1214.39  4982.2 1214.69  4994.6 1213.57
  4994.8 1213.07  4998.3 1213.07  4998.6 1213.57    5003 1213.66  5010.9 1215.08
  5017.4 1215.26  5025.3 1214.76  5089.2 1214.28  5124.4 1215.39    5217 1219.67
  5237.8 1221.24  5245.7 1222.78  5252.2 1222.36  5337.2 1228.23  5411.2  1229.5
#Mann= 3 ,-1 , 0
  4536.6     .05       0  4994.6     .05       0  4998.6     .05       0
Bank Sta=4994.6,4998.6
XS Rating Curve= 0 ,0
Exp/Cntr=0.3,0.1

Type RM Length L Ch R = 1 ,38336   ,290,290,290
BEGIN DESCRIPTION:
Mapping XS e47c0601
END DESCRIPTION:
XS GIS Cut Line= 2
      2828119.56     10214442.56      2828774.47     10214114.46
#Sta/Elev= 30
  4649.4 1215.11  4705.3 1213.75  4734.5 1213.61    4750 1213.17  4756.9  1213.4
  4779.3 1212.72    4817 1212.84  4878.5 1212.31  4906.4 1212.68  4913.5 1212.24
  4928.8 1212.61  4973.5 1212.68  4990.2 1211.82  4993.8 1211.13  4994.1 1210.63
  4997.6 1210.63  4997.8 1211.13    5003 1211.56  5025.4 1212.02  5159.6 1211.81
  5181.9 1212.88  5191.3 1212.73  5196.9  1213.4    5236 1214.51    5249  1215.6
  5280.7 1217.05  5286.3 1217.94    5331 1221.37  5360.9 1223.15  5381.9 1223.81
#Mann= 3 , 0 , 0
  4649.4     .05       0  4973.5     .03       0  5025.4     .05       0
Bank Sta=4973.5,5025.4
XS Rating Curve= 0 ,0
Exp/Cntr=0.3,0.1

Type RM Length L Ch R = 1 ,38046   ,177,177,177
BEGIN DESCRIPTION:
Mapping XS 88aecae9
END DESCRIPTION:
XS GIS Cut Line= 3
      2828116.92     10214510.28      2828573.96     10214572.78
      2828947.67     10214572.78
#Sta/Elev= 30
  4640.6 1215.07  4669.6  1214.8  4679.7 1214.25  4701.7 1213.78  4750.4 1213.14
  4800.8 1211.34  4846.1  1210.6  4871.5 1209.72  4911.9 1209.37  4923.4 1208.88
  4942.1 1208.91  4962.3 1208.09  4982.5  1208.6  4995.6 1207.73  5000.7 1206.63
    5001 1206.13  5004.5 1206.13  5004.7 1206.63    5033  1208.3  5062.8 1208.46
  5100.2 1207.58  5113.6 1207.92  5143.6 1207.43  5223.6 1207.28  5233.6  1207.5
  5273.6 1206.71  5353.6 1209.12  5363.6 1209.18  5453.6 1212.44  5475.6 1212.32
#Mann= 3 , 0 , 0
  4640.6     .05       0  4982.5     .03       0    5033     .05       0
Bank Sta=4982.5,5033
XS Rating Curve= 0 ,0
Exp/Cntr=0.3,0.1

Type RM Length L Ch R = 1 ,37869   ,317,317,317
BEGIN DESCRIPTION:
Mapping XS 4d338741
END DESCRIPTION:
XS GIS Cut Line= 3
       2828100.3     10214736.68      2828265.41      10214714.4
      2828890.63     10214751.05
#Sta/Elev= 30
  4691.3 1209.73  4727.6 1211.01  4770.7 1212.19  4807.7 1211.85  4855.5 1210.18
  4917.3 1208.53  4922.3 1208.68  4968.4 1206.51  4978.4 1205.93  4988.4 1204.76
  5006.4 1201.56  5006.7 1201.06  5010.2 1201.06  5010.4 1201.56  5018.5 1204.33
  5028.5 1205.71  5038.5 1206.21  5087.9 1206.79  5138.7 1205.87  5148.7  1206.1
  5263.5 1205.46  5278.9 1204.37  5298.9 1205.27    5309 1204.89    5329 1205.23
    5359 1204.72  5379.1  1205.7  5419.1 1206.86  5434.1 1206.87  5484.2 1208.17
#Mann= 5 ,-1 , 0
  4691.3     .05       0  4727.6     .12       0  4770.7     .05       0
  4968.4     .03       0  5038.5     .05       0
Bank Sta=4968.4,5038.5
XS Rating Curve= 0 ,0
Exp/Cntr=0.3,0.1

Type RM Length L Ch R = 1 ,37552   ,509,509,509
BEGIN DESCRIPTION:
Mapping XS 8d2c403b
END DESCRIPTION:
XS GIS Cut Line= 2
      2828157.92     10214799.33      2828552.24     10215111.93
#Sta/Elev= 30
  4654.1 1210.75  4669.3 1209.87  4683.7 1210.61  4685.4 1210.38  4690.1 1209.76
  4698.2    1210    4727 1209.32  4733.4 1208.88  4762.3 1208.27  4768.6 1207.38
  4804.4 1205.98  4811.9 1206.03  4818.3 1205.62  4826.4 1205.67  4847.2 1204.93
  4855.2 1205.03  4882.4 1204.44  4890.5 1204.54  4932.1 1202.88 4970.12  1197.1
 4982.51 1196.38  5002.5 1196.06 5018.99 1196.22  5046.8 1202.57  5068.3 1202.49
  5097.2 1201.61  5110.6 1201.96  5132.4 1202.04  5146.8 1201.36  5157.3 1201.27
#Mann= 4 ,-1 , 0
  4654.1     .12       0  4685.4     .05       0  4932.1     .03       0
  5046.8     .05       0
Bank Sta=4932.1,5046.8
XS Rating Curve= 0 ,0
Exp/Cntr=0.3,0.1

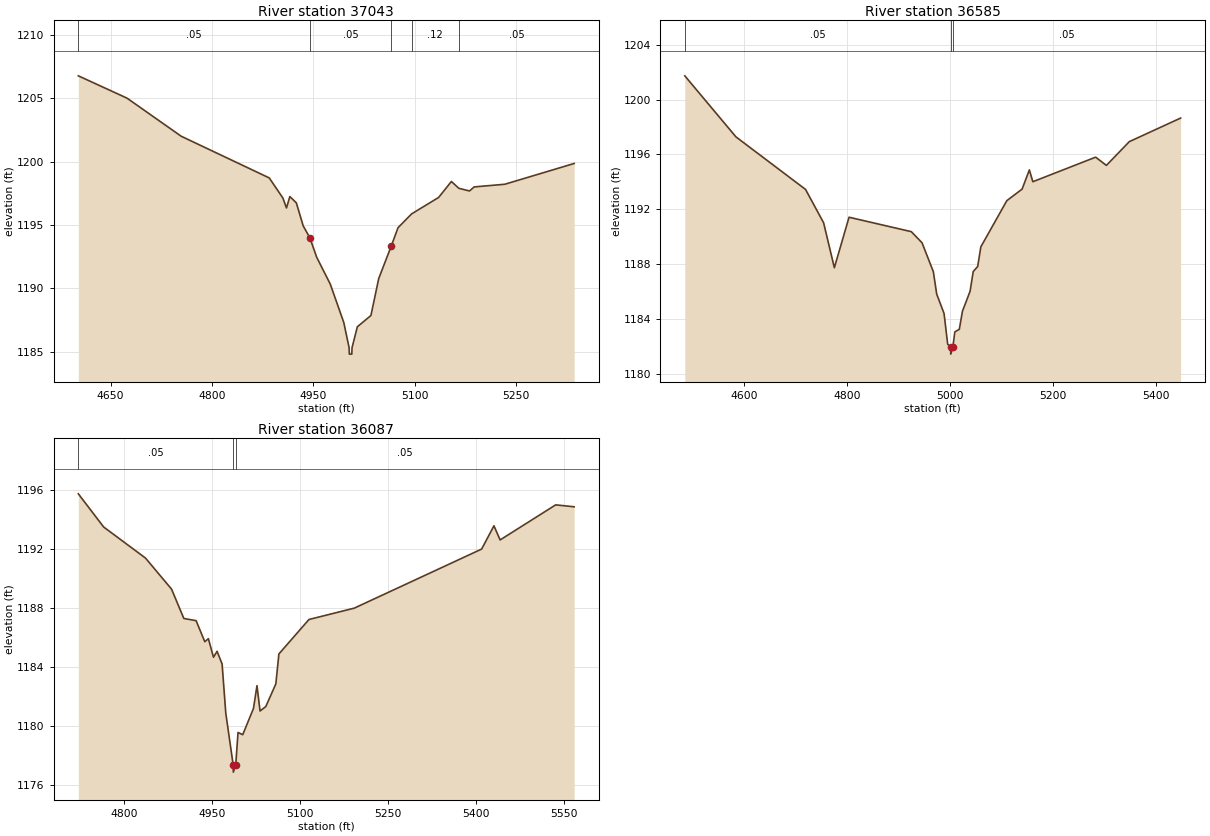
Type RM Length L Ch R = 1 ,37043   ,458,458,458
BEGIN DESCRIPTION:
Mapping XS 3a6f05cb
END DESCRIPTION:
XS GIS Cut Line= 3
      2827653.86     10215254.86      2828208.33     10215296.78
      2828371.12     10215225.15
#Sta/Elev= 30
  4602.3 1206.78  4674.3 1205.02  4754.6 1202.01  4884.9 1198.72    4905 1197.14
  4910.4 1196.35  4915.4 1197.25    4925 1196.75  4935.1 1194.94  4945.1 1193.98
  4955.1 1192.46  4975.2 1190.34  4995.2 1187.31  5003.1 1185.31  5003.4 1184.81
  5007.1 1184.81  5007.4 1185.31  5015.3 1186.97  5035.4 1187.86  5046.9 1190.77
  5065.4 1193.33  5075.5 1194.79  5095.6 1195.88  5135.6 1197.18  5154.5 1198.44
  5165.5  1197.9  5181.3 1197.69  5188.2 1198.01  5233.5 1198.22  5336.2 1199.86
#Mann= 5 ,-1 , 0
  4602.3     .05       0  4945.1     .05       0  5065.4     .05       0
  5095.6     .12       0  5165.5     .05       0
Bank Sta=4945.1,5065.4
XS Rating Curve= 0 ,0
Exp/Cntr=0.3,0.1

Type RM Length L Ch R = 1 ,36585   ,498,498,498
BEGIN DESCRIPTION:
BYRNES CREEK 65.0
END DESCRIPTION:
XS GIS Cut Line= 3
      2827805.71     10216003.09       2828197.5       10215669.
      2828455.68     10215303.12
#Sta/Elev= 30
  4485.1 1201.73  4584.4 1197.28  4719.5 1193.45  4754.6 1191.02  4775.5 1187.74
    4804 1191.42  4924.8 1190.37  4945.7 1189.56  4967.7 1187.45  4974.2 1185.82
  4988.5  1184.4  4995.5 1182.17  5001.2 1181.94  5001.5 1181.44  5005.5 1181.94
  5009.4 1183.06  5018.1 1183.25  5024.2 1184.57    5039 1186.02  5045.1 1187.46
  5053.8 1187.83  5059.9 1189.26  5110.4 1192.63    5140 1193.47  5154.1 1194.87
  5160.9 1194.01  5282.8  1195.8  5303.7  1195.2  5348.1 1196.93  5447.8 1198.65
#Mann= 3 ,-1 , 0
  4485.1     .05       0  5001.2     .05       0  5005.5     .05       0
Bank Sta=5001.2,5005.5
XS Rating Curve= 0 ,0
Exp/Cntr=0.3,0.1

Type RM Length L Ch R = 1 ,36087   ,468,468,468
BEGIN DESCRIPTION:
BYRNES CREEK 64.0
END DESCRIPTION:
XS GIS Cut Line= 3
      2828155.71     10216253.09      2828382.25       10216093.
       2828555.7     10215553.08
#Sta/Elev= 30
  4722.6 1195.73  4765.7 1193.48    4837 1191.37  4881.4 1189.26  4902.3 1187.27
  4923.2 1187.12    4938 1185.69  4944.1  1185.9  4952.8 1184.64  4958.9 1185.04
  4967.5 1184.18  4973.7 1180.86  4986.3 1177.34  4986.6 1176.84  4990.7 1177.34
  4994.6 1179.53  5002.6 1179.38  5020.9 1181.16  5026.9 1182.71  5032.1 1180.99
  5041.9 1181.29    5059 1182.83  5064.2 1184.86  5115.4  1187.2  5192.6 1187.97
  5409.5 1191.98  5430.5 1193.56    5441  1192.6  5535.6 1194.98  5567.1 1194.85
#Mann= 3 ,-1 , 0
  4722.6     .05       0  4986.3     .05       0  4990.7     .05       0
Bank Sta=4986.3,4990.7
XS Rating Curve= 0 ,0
Exp/Cntr=0.3,0.1