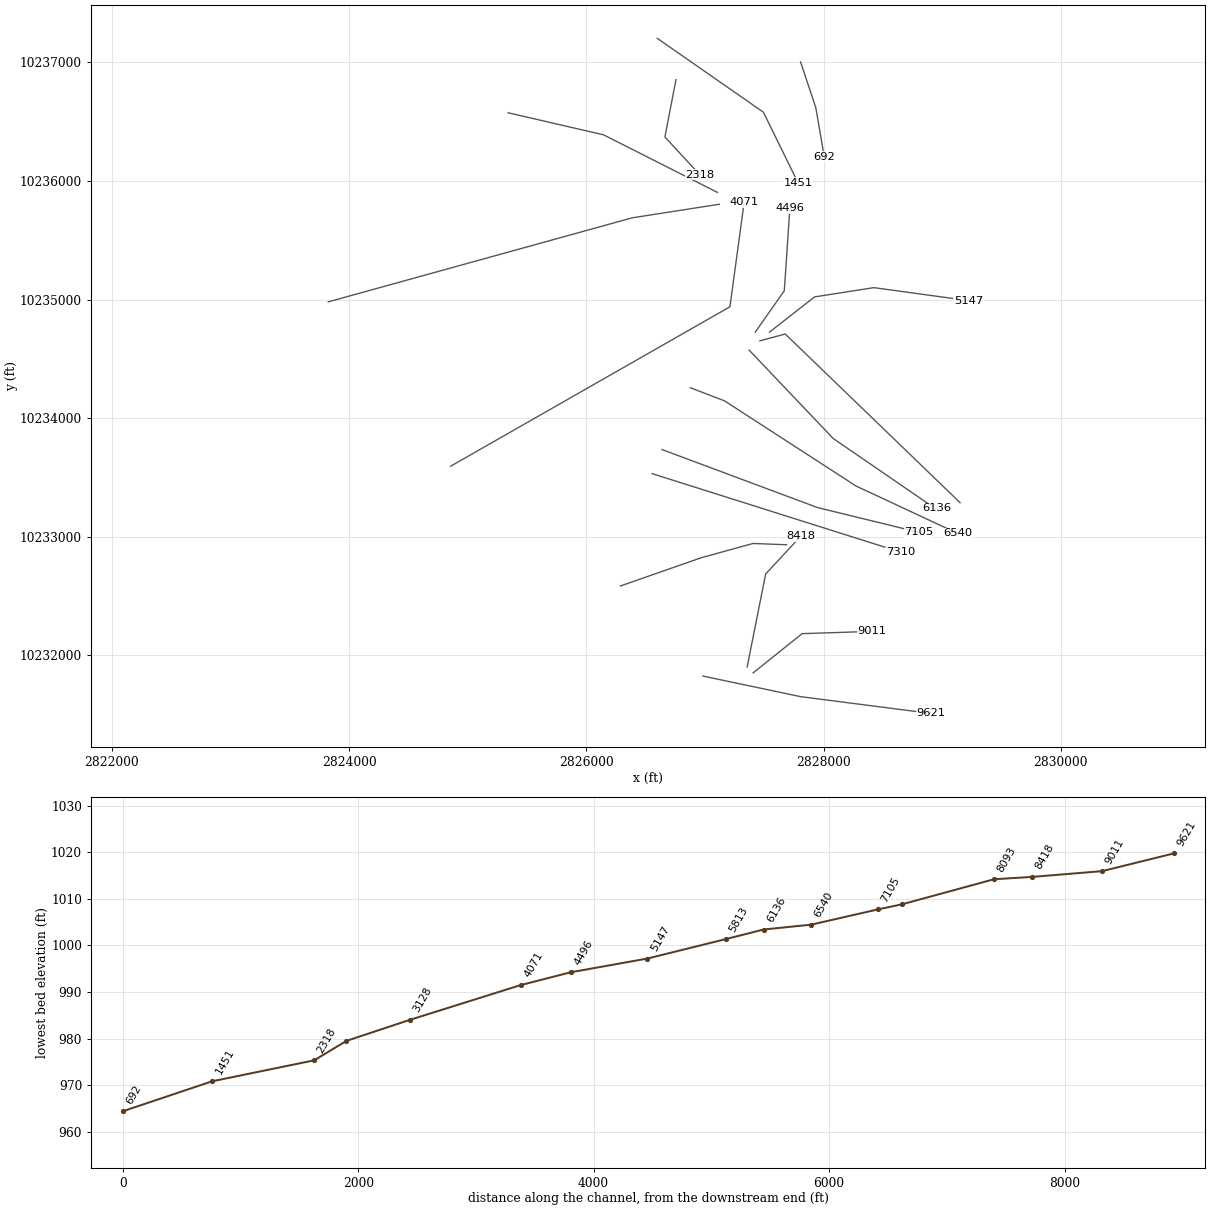
HEC-RAS study BYRNES CREEK.prj: BYRNES CREEK Base Level Engineering

--- BYRNES CREEK.g01 (geometry) --- (continued)

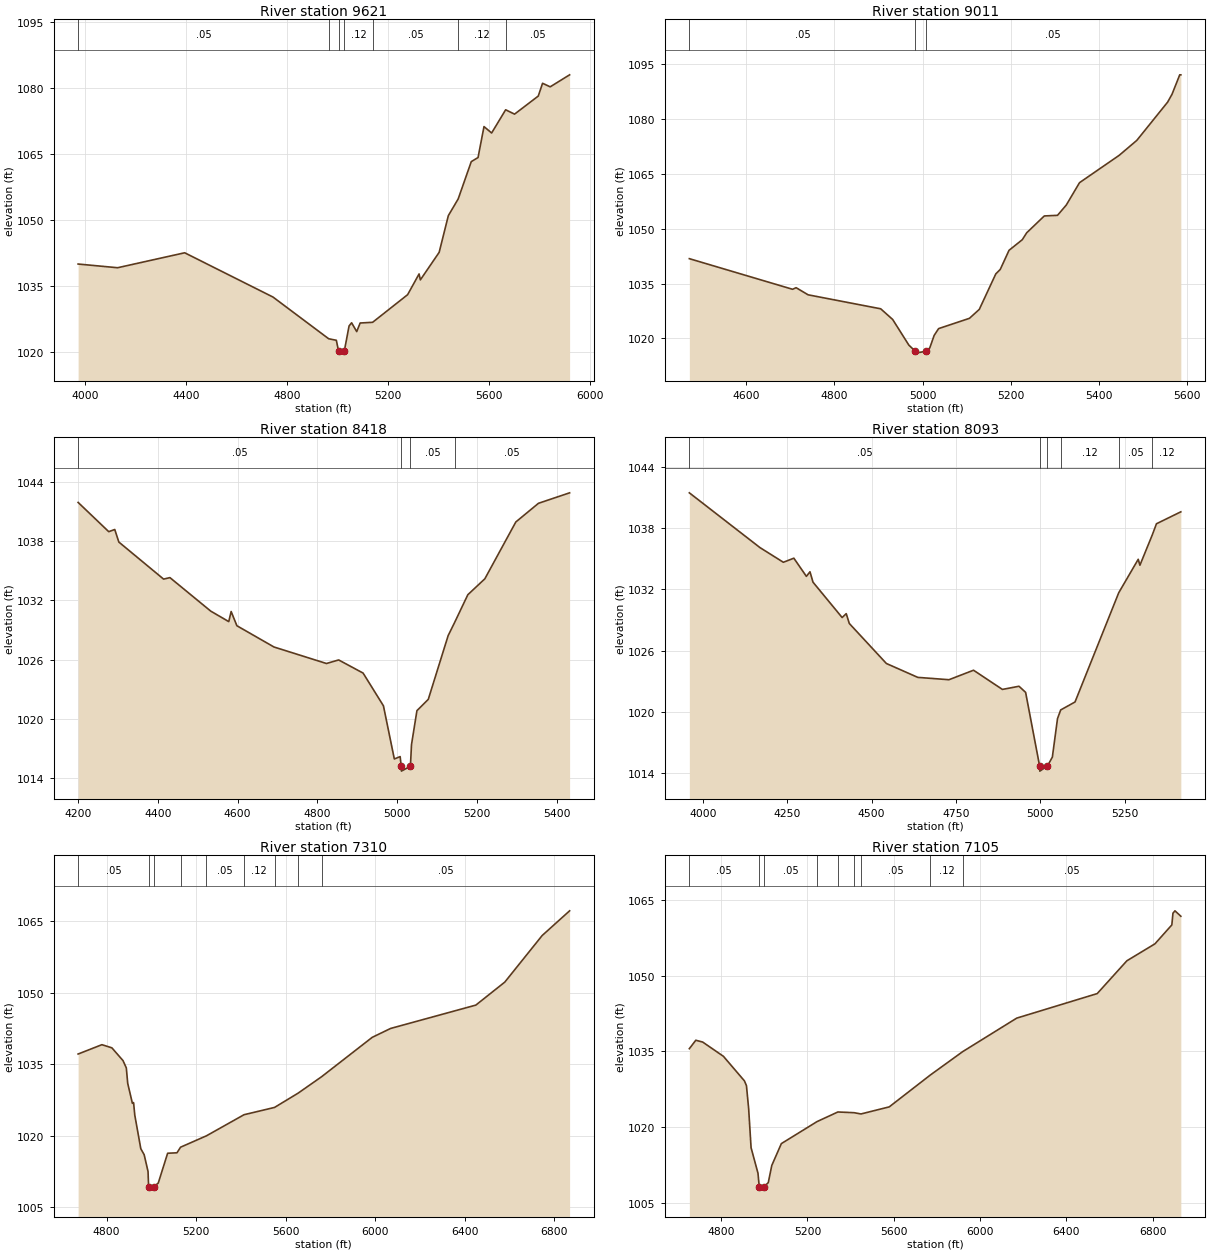
Type RM Length L Ch R = 1 ,9621    ,610,610,610
BEGIN DESCRIPTION:
Mapping XS 3ac1b4be
END DESCRIPTION:
XS GIS Cut Line= 3
      2826982.63     10231826.53      2827807.31     10231652.92
      2828901.92     10231512.03
#Sta/Elev= 30
    3973 1040.02  4129.4 1039.18  4395.1 1042.58  4744.8 1032.51  4965.2 1023.03
  4995.6 1022.68  5004.3 1020.26  5004.8 1019.76  5027.3 1020.26    5046 1025.93
  5056.1 1026.66  5076.3 1024.65  5089.9 1026.61  5139.3 1026.77  5277.9 1033.05
  5323.3 1037.77  5328.4 1036.42  5402.8 1042.68  5439.2 1051.03  5478.1 1054.82
    5530 1063.31  5556.8 1064.24  5580.4 1071.28  5610.6 1069.82  5666.1  1075.1
  5701.4 1074.11  5795.3 1078.22  5812.3 1081.13  5842.5 1080.32  5919.4 1083.05
#Mann= 7 ,-1 , 0
    3973     .05       0  4965.2     .12       0  5004.3     .07       0
  5027.3     .12       0  5139.3     .05       0  5478.1     .12       0
  5666.1     .05       0
Bank Sta=5004.3,5027.3
XS Rating Curve= 0 ,0
Exp/Cntr=0.3,0.1

Type RM Length L Ch R = 1 ,9011    ,593,593,593
BEGIN DESCRIPTION:
BYRNES CREEK 14.0
END DESCRIPTION:
XS GIS Cut Line= 3
      2827405.72     10231853.14      2827819.25       10232184.
      2828405.64     10232203.11
#Sta/Elev= 30
  4470.4  1041.8  4704.9 1033.42  4712.9 1033.86  4740.1 1031.91    4905 1028.08
  4932.2 1025.16    4969 1018.14  4983.7 1016.45  4984.2 1015.95  5006.8 1016.45
  5016.4 1017.36  5026.4 1020.79  5036.5 1022.66  5106.5 1025.47  5128.9 1027.91
  5166.5 1037.65  5176.5 1038.84  5196.5 1044.09  5226.6 1046.99  5236.6 1048.88
  5276.6 1053.49  5306.6 1053.66  5326.6 1056.49  5356.6  1062.6  5446.7 1070.08
  5486.7 1074.17  5556.7 1084.64  5566.7  1086.8  5584.2 1092.11  5586.7 1092.11
#Mann= 3 ,-1 , 0
  4470.4     .05       0  4983.7     .03       0  5006.8     .05       0
Bank Sta=4983.7,5006.8
XS Rating Curve= 0 ,0
Exp/Cntr=0.3,0.1

Type RM Length L Ch R = 1 ,8418    ,325,325,325
BEGIN DESCRIPTION:
BYRNES CREEK 13.0
END DESCRIPTION:
XS GIS Cut Line= 3
      2827355.68     10231903.09      2827511.75       10232687.
      2827805.72     10233003.15
#Sta/Elev= 30
  4200.7 1041.91  4277.4 1038.95  4292.5 1039.17  4302.7  1037.9  4414.8 1034.15
  4430.7  1034.3  4532.9 1030.91    4578 1029.85    4584 1030.87  4598.4 1029.43
  4691.3 1027.28  4822.7 1025.61  4853.3 1025.97  4914.5 1024.64  4965.4 1021.33
  4992.7 1015.95  5007.3 1016.19  5009.9 1015.22  5010.4 1014.72    5033 1015.22
  5035.7  1017.4  5049.3 1020.84  5077.7 1021.98  5127.5 1028.43  5143.8 1029.77
  5176.8 1032.57  5219.4 1034.18    5297 1039.93  5353.7 1041.82  5431.7 1042.88
#Mann= 4 ,-1 , 0
  4200.7     .05       0  5009.9     .05       0    5033     .05       0
  5143.8     .05       0
Bank Sta=5009.9,5033
XS Rating Curve= 0 ,0
Exp/Cntr=0.3,0.1

Type RM Length L Ch R = 1 ,8093    ,783,783,783
BEGIN DESCRIPTION:
Mapping XS ce40669e
END DESCRIPTION:
XS GIS Cut Line= 4
      2826288.17     10232586.06       2826971.8     10232824.79
      2827405.83     10232944.15      2827687.97      10232933.3
#Sta/Elev= 30
  3959.7 1041.46  4168.9  1036.1  4238.3 1034.66  4269.4 1035.06  4306.6 1033.28
  4317.2 1033.73  4326.2 1032.71  4412.5 1029.25  4424.7 1029.63  4433.7 1028.67
  4543.6 1024.75  4636.7 1023.39  4729.1 1023.16  4801.9 1024.09  4887.5 1022.21
  4936.7 1022.52  4956.3 1021.92  4997.8 1014.71  4998.3 1014.21  5020.9 1014.71
  5035.5 1015.58  5050.8 1019.35  5060.2  1020.2  5102.7 1020.98  5232.3 1031.68
    5290 1034.95    5295 1034.37  5331.3 1037.31    5344 1038.43  5416.3  1039.6
#Mann= 6 ,-1 , 0
  3959.7     .05       0  4997.8     .05       0  5020.9     .05       0
  5060.2     .12       0  5232.3     .05       0  5331.3     .12       0
Bank Sta=4997.8,5020.9
XS Rating Curve= 0 ,0
Exp/Cntr=0.3,0.1

Type RM Length L Ch R = 1 ,7310    ,205,205,205
BEGIN DESCRIPTION:
BYRNES CREEK 11.0
END DESCRIPTION:
XS GIS Cut Line= 2
      2826554.36     10233532.73      2828648.06     10232871.29
#Sta/Elev= 30
  4673.2 1037.18  4779.5 1039.14    4824 1038.48  4873.9 1035.79  4888.6 1034.25
  4894.8 1031.02  4915.7 1026.83    4921 1026.99  4926.3 1024.37  4953.3  1017.3
  4968.2 1016.06  4985.6 1012.52  4988.1 1009.32  4988.6 1008.82  5011.3 1009.32
  5031.2 1010.09  5073.1 1016.35  5114.9 1016.45  5130.8 1017.62  5246.5 1020.01
  5414.4 1024.44  5550.8 1025.97  5655.8 1028.96  5760.8 1032.41    5987 1040.68
  6069.4 1042.55    6450 1047.45  6579.4 1052.28  6746.2 1062.05  6868.9 1067.24
#Mann= 9 ,-1 , 0
  4673.2     .05       0  4988.1     .05       0  5011.3     .05       0
  5130.8     .12       0  5246.5     .05       0  5414.4     .12       0
  5550.8     .05       0  5655.8     .12       0  5760.8     .05       0
Bank Sta=4988.1,5011.3
XS Rating Curve= 0 ,0
Exp/Cntr=0.3,0.1

Type RM Length L Ch R = 1 ,7105    ,565,565,565
BEGIN DESCRIPTION:
BYRNES CREEK 10.0
END DESCRIPTION:
XS GIS Cut Line= 3
      2826637.67     10233735.86      2827950.14     10233246.29
      2828802.16     10233038.48
#Sta/Elev= 30
  4652.5 1035.53  4682.4  1037.2  4714.4 1036.84  4810.5 1034.02  4907.7 1029.16
  4917.2  1028.2  4927.4 1023.64  4938.6 1015.93  4970.6 1010.88  4976.4 1008.23
  4976.9 1007.73  4999.6 1008.23  5018.3 1009.02  5034.6 1012.42  5078.9 1016.74
  5244.4  1021.1  5340.9    1023  5415.8 1022.86    5448 1022.61  5578.9 1024.01
  5769.4 1030.32  5920.1 1034.97  6169.7 1041.58  6542.8 1046.44  6680.2 1052.93
  6810.4 1056.29  6888.6 1060.03  6893.8 1062.35  6903.1 1062.82  6930.3 1061.75
#Mann= 9 ,-1 , 0
  4652.5     .05       0  4976.4     .03       0  4999.6     .05       0
  5244.4     .12       0  5340.9     .05       0  5415.8     .12       0
    5448     .05       0  5769.4     .12       0  5920.1     .05       0
Bank Sta=4976.4,4999.6
XS Rating Curve= 0 ,0
Exp/Cntr=0.3,0.1

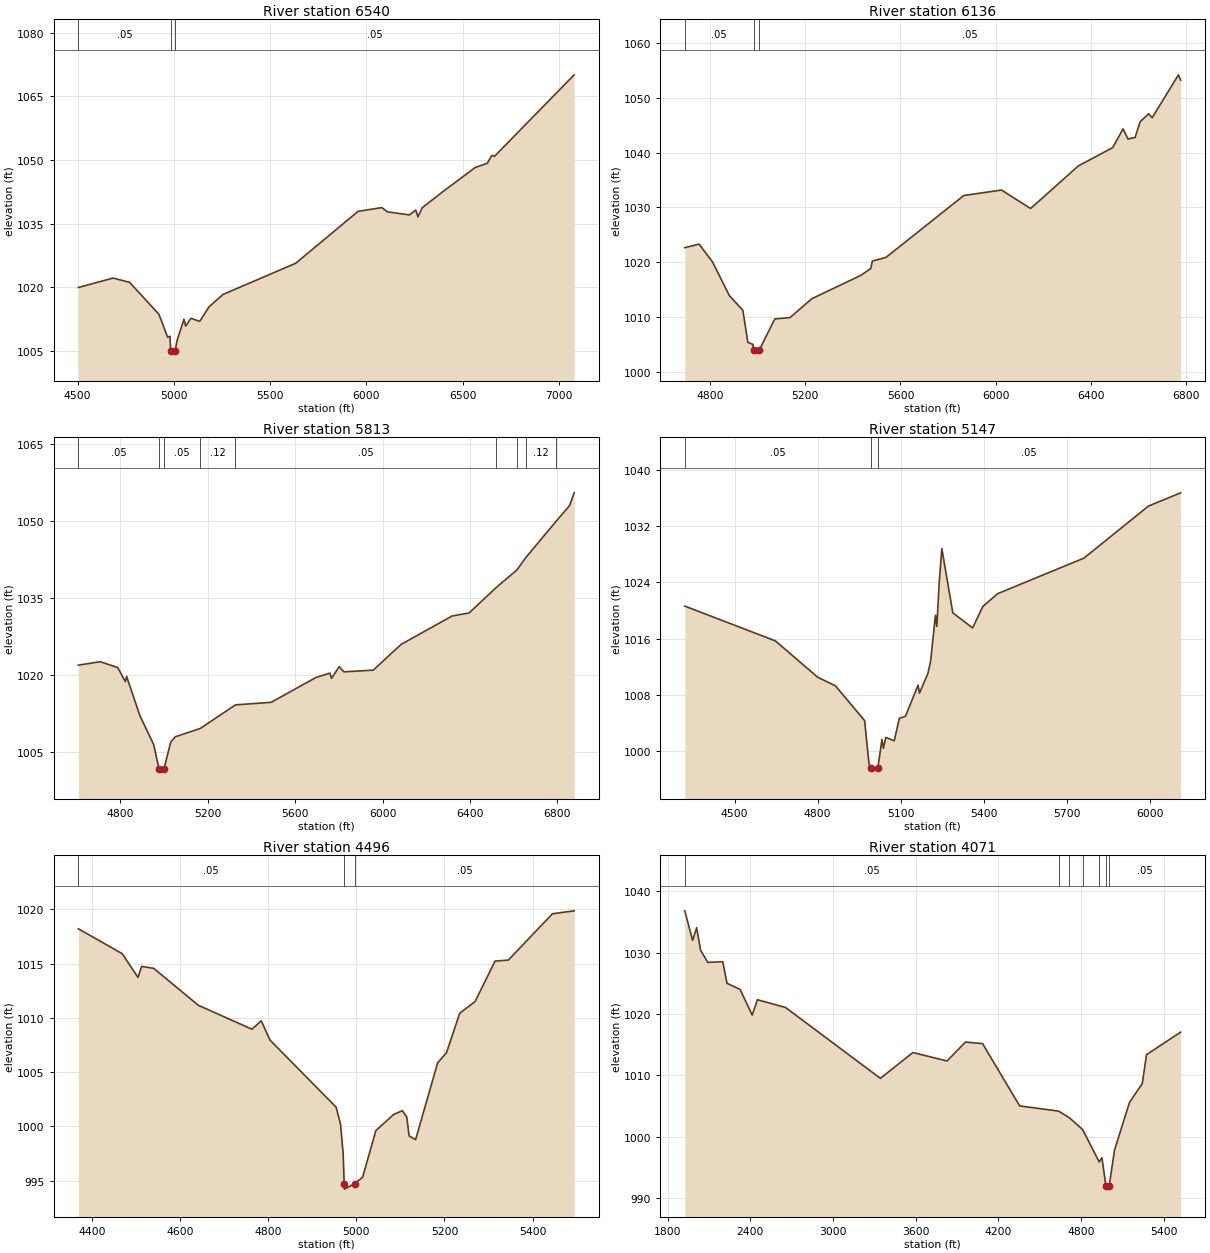
Type RM Length L Ch R = 1 ,6540    ,404,404,404
BEGIN DESCRIPTION:
Mapping XS 6a666ff3
END DESCRIPTION:
XS GIS Cut Line= 4
      2826877.26     10234256.69      2827165.21     10234146.14
      2828273.06     10233428.58      2829130.97     10233028.22
#Sta/Elev= 30
  4503.4 1019.94  4683.8 1022.16  4769.5 1021.16  4922.1 1013.62  4967.3  1008.2
  4979.5 1008.43    4983 1004.96  4983.5 1004.46  5006.3 1004.96  5015.7 1007.35
    5052 1012.45  5061.2 1010.84  5088.3 1012.68  5133.7 1011.94  5181.9 1015.36
  5254.4 1018.29  5632.3 1025.65  5956.2 1037.89  6079.4 1038.78  6109.7 1037.77
  6222.5 1037.06  6256.3 1038.19  6267.1  1036.6  6289.2 1038.74  6399.5 1042.63
    6565 1048.25  6627.6 1049.23  6650.5 1051.08  6664.4 1050.85  7078.5 1070.09
#Mann= 3 ,-1 , 0
  4503.4     .05       0    4983     .05       0  5006.3     .05       0
Bank Sta=4983,5006.3
XS Rating Curve= 0 ,0
Exp/Cntr=0.3,0.1

Type RM Length L Ch R = 1 ,6136    ,323,323,323
BEGIN DESCRIPTION:
Mapping XS 256a294f
END DESCRIPTION:
XS GIS Cut Line= 4
      2827372.05     10234574.39      2828080.35     10233829.62
      2828944.94     10233235.87      2828950.15     10233241.09
#Sta/Elev= 30
  4693.4 1022.66  4753.4 1023.32    4810 1020.05  4880.8  1013.9  4937.4 1011.25
  4958.4 1005.38  4979.9 1005.01  4982.4 1003.92  4982.9 1003.42  5005.7 1003.92
  5071.7 1009.66  5135.6  1009.9  5227.4 1013.35  5432.5 1017.59  5474.9 1018.85
  5481.8 1020.22  5538.5 1020.87  5866.2 1032.18  6024.5 1033.18    6147 1029.81
  6347.3 1037.57  6491.9 1040.92  6535.4 1044.33  6556.4 1042.49  6586.2 1042.78
  6607.1 1045.63    6643 1047.09  6657.9 1046.37  6768.1  1054.2  6777.4 1053.25
#Mann= 3 ,-1 , 0
  4693.4     .05       0  4982.4     .03       0  5005.7     .05       0
Bank Sta=4982.4,5005.7
XS Rating Curve= 0 ,0
Exp/Cntr=0.3,0.1

Type RM Length L Ch R = 1 ,5813    ,666,666,666
BEGIN DESCRIPTION:
Mapping XS 8f3d47d2
END DESCRIPTION:
XS GIS Cut Line= 3
      2827463.28     10234652.26      2827676.83     10234709.55
      2829150.51     10233287.95
#Sta/Elev= 30
  4608.2 1021.94  4708.5 1022.61  4788.5 1021.47  4823.3 1018.74  4829.3 1019.74
  4889.6 1012.16  4953.2 1006.48    4977 1001.85  4977.5 1001.35  5000.3 1001.85
  5031.1 1007.02  5052.2 1008.03  5165.8 1009.63  5327.2 1014.22  5490.8 1014.72
  5695.8 1019.55  5759.4  1020.4  5766.6 1019.37  5801.8 1021.65  5823.2 1020.64
  5957.5 1020.97  6084.8 1025.96  6318.1 1031.49  6396.1 1032.08  6520.8 1037.04
  6615.9 1040.47  6656.3 1042.88  6791.8 1049.76  6855.8 1052.94  6876.9 1055.42
#Mann= 9 ,-1 , 0
  4608.2     .05       0    4977     .05       0  5000.3     .05       0
  5165.8     .12       0  5327.2     .05       0  6520.8     .12       0
  6615.9     .05       0  6656.3     .12       0  6791.8     .05       0
Bank Sta=4977,5000.3
XS Rating Curve= 0 ,0
Exp/Cntr=0.3,0.1

Type RM Length L Ch R = 1 ,5147    ,651,651,651
BEGIN DESCRIPTION:
Mapping XS b3fd8918
END DESCRIPTION:
XS GIS Cut Line= 4
      2827543.93     10234725.49       2827924.1     10235022.33
       2828424.1     10235100.46      2829220.83      10234991.1
#Sta/Elev= 30
  4319.9 1020.63  4647.4 1015.69  4800.1 1010.53  4864.6  1009.3    4970 1004.36
    4986  998.17  4994.6  997.68  4995.1  997.18    5018  997.68  5032.8 1001.69
  5037.8 1000.43  5046.7 1001.97  5077.1 1001.49  5095.5 1004.68  5117.6 1004.97
  5163.3  1009.4  5168.4 1008.28  5198.6 1011.04  5208.7 1012.83  5226.1 1019.33
  5231.2 1017.74  5239.1 1023.68  5249.2 1028.81  5288.9 1019.68  5360.4 1017.53
  5397.4 1020.58  5451.2  1022.4  5762.9 1027.45  5996.3 1034.85  6112.5 1036.73
#Mann= 3 ,-1 , 0
  4319.9     .05       0  4994.6     .05       0    5018     .05       0
Bank Sta=4994.6,5018
XS Rating Curve= 0 ,0
Exp/Cntr=0.3,0.1

Type RM Length L Ch R = 1 ,4496    ,425,425,425
BEGIN DESCRIPTION:
BYRNES CREEK 8.0
END DESCRIPTION:
XS GIS Cut Line= 3
       2827424.1     10234725.46      2827668.89     10235074.41
      2827715.77     10235772.29
#Sta/Elev= 30
  4368.7 1018.22  4468.4 1015.92  4504.2 1013.73  4512.4 1014.75  4539.9 1014.57
    4641 1011.17    4763 1008.96    4784 1009.74  4803.7 1007.97    4954 1001.78
    4964 1000.21    4970  997.49  4972.3  994.73  4972.8  994.23  4995.8  994.73
  5014.1  995.32  5044.2  999.62  5084.3  1001.1  5104.3 1001.46  5114.4 1000.87
  5119.7  999.13  5134.4  998.79  5184.5 1005.87  5204.6  1006.8  5234.6 1010.44
  5269.5 1011.51  5314.8 1015.24  5344.9 1015.33  5445.1  1019.6  5494.4 1019.87
#Mann= 3 ,-1 , 0
  4368.7     .05       0  4972.3     .05       0  4995.8     .05       0
Bank Sta=4972.3,4995.8
XS Rating Curve= 0 ,0
Exp/Cntr=0.3,0.1

Type RM Length L Ch R = 1 ,4071    ,943,943,943
BEGIN DESCRIPTION:
BYRNES CREEK 7.0
END DESCRIPTION:
XS GIS Cut Line= 3
      2824856.38     10233595.24      2827210.56       10234939.
      2827330.28      10235818.7
#Sta/Elev= 30
  1924.5 1036.81  1981.3    1032  2010.5 1034.07  2038.8 1030.42  2091.2 1028.41
    2200 1028.52  2230.9    1025  2326.7 1023.99  2413.7 1019.82  2451.2 1022.33
  2655.7 1021.07    3344 1009.52  3580.2 1013.73  3827.9 1012.35  3961.7 1015.44
  4085.7 1015.18    4355 1005.03  4637.2 1004.19  4715.4 1003.11  4811.8 1001.18
  4932.2  995.91  4952.2  996.59  4980.8  991.98  4981.3  991.48  5004.3  991.98
    5043  997.82  5152.1 1005.61  5244.9 1008.68  5275.2 1013.38    5523 1017.05
#Mann= 7 ,-1 , 0
  1924.5     .05       0  4637.2     .12       0  4715.4     .05       0
  4811.8     .12       0  4932.2     .05       0  4980.8     .03       0
  5004.3     .05       0
Bank Sta=4980.8,5004.3
XS Rating Curve= 0 ,0
Exp/Cntr=0.3,0.1

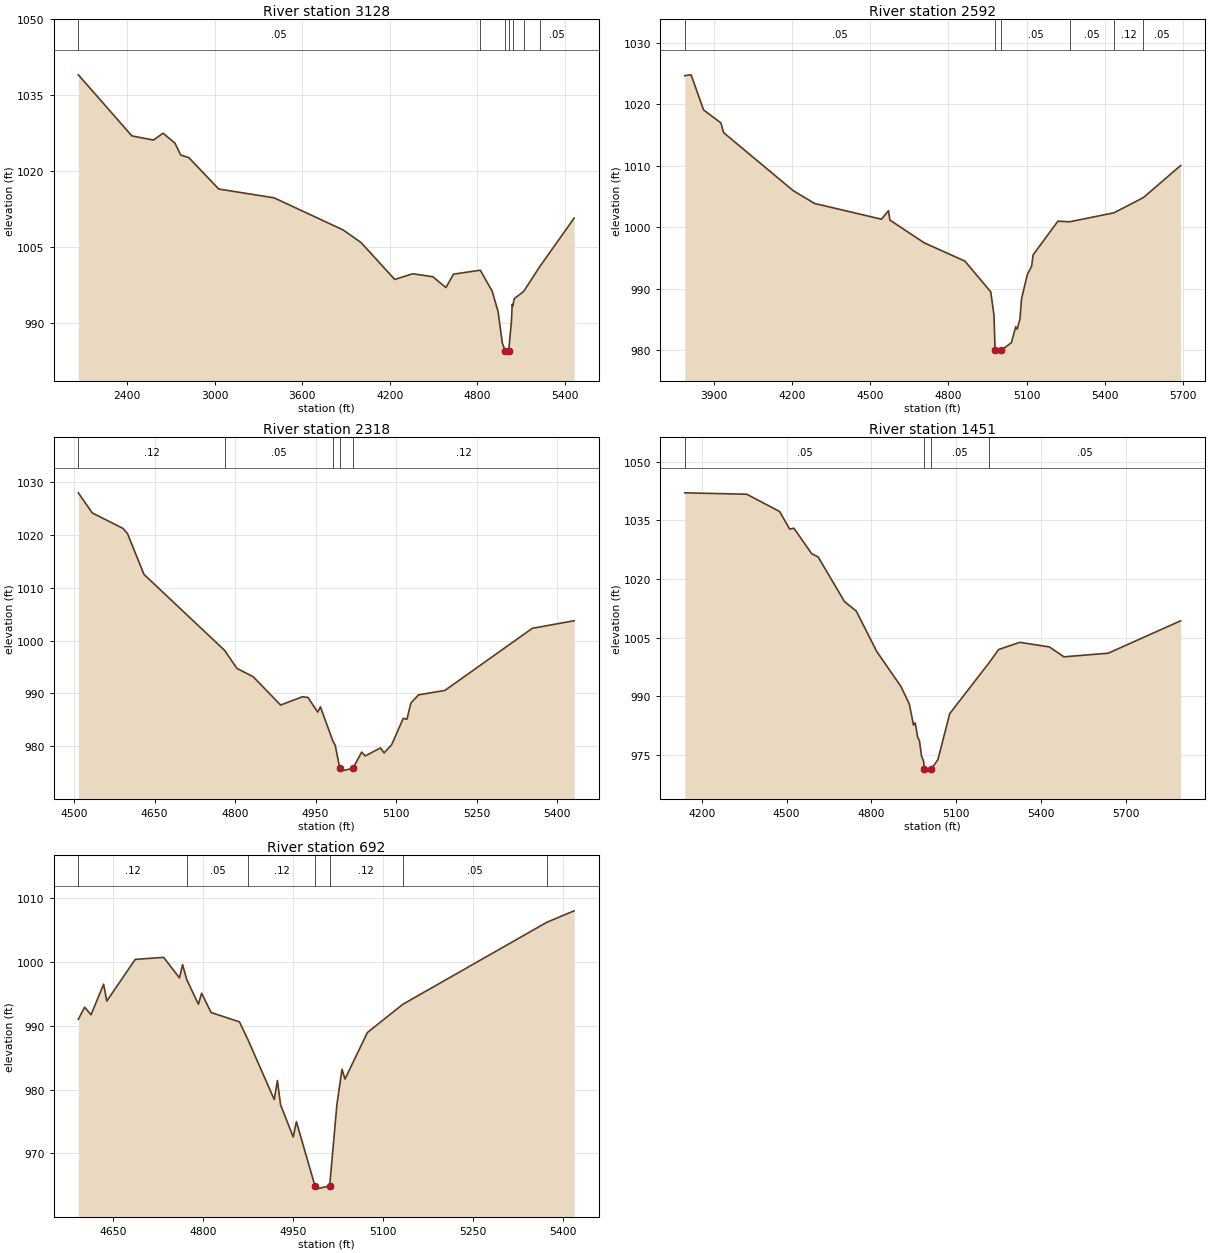
Type RM Length L Ch R = 1 ,3128    ,536,536,536
BEGIN DESCRIPTION:
BYRNES CREEK 6.0
END DESCRIPTION:
XS GIS Cut Line= 3
      2823825.17     10234980.67      2826387.64       10235689.
      2827121.39     10235803.48
#Sta/Elev= 30
  2064.1 1039.05  2431.4 1026.97  2579.1 1026.15  2645.6  1027.5  2726.8 1025.54
  2766.3 1023.19    2822 1022.67  3027.3 1016.46  3406.9 1014.72  3880.3 1008.37
  4002.9 1005.89  4234.8  998.57  4357.5   999.7  4495.9  999.11  4585.8  996.97
  4637.6  999.62  4821.4  1000.4  4902.9  996.25  4943.4  992.22  4972.5  985.99
    4992   984.5  4992.5     984  5016.1   984.5  5034.4  990.02  5040.4  993.64
  5044.1   993.3  5054.7  994.78  5118.7  996.19  5229.4 1001.11  5465.3 1010.71
#Mann= 7 ,-1 , 0
  2064.1     .05       0  4821.4     .12       0    4992     .07       0
  5016.1     .12       0  5044.1     .05       0  5118.7     .12       0
  5229.4     .05       0
Bank Sta=4992,5016.1
XS Rating Curve= 0 ,0
Exp/Cntr=0.3,0.1

Type RM Length L Ch R = 1 ,2592    ,274,274,274
BEGIN DESCRIPTION:
BYRNES CREEK 5.0
END DESCRIPTION:
XS GIS Cut Line= 3
      2825340.76     10236574.42      2826145.07     10236388.51
      2827105.68     10235903.11
#Sta/Elev= 30
  3788.9 1024.62  3813.1 1024.75    3861 1019.04  3927.4 1016.93  3937.6 1015.36
  4204.5 1005.93  4286.6 1003.84  4543.2 1001.28  4570.3 1002.67  4575.5 1001.14
  4707.2  997.44  4863.2  994.47  4962.4  989.48  4974.7  985.71  4979.1  980.01
  4979.6  979.51  5003.5  980.01  5041.5   981.2  5058.2   983.8  5063.8  983.41
  5074.5  985.06  5080.5  988.35  5102.8  992.28  5119.3  993.66  5125.1   995.5
  5220.1 1000.96    5265 1000.86    5435 1002.32  5548.1  1004.8  5690.7 1010.01
#Mann= 6 ,-1 , 0
  3788.9     .05       0  4979.1     .05       0  5003.5     .05       0
    5265     .05       0    5435     .12       0  5548.1     .05       0
Bank Sta=4979.1,5003.5
XS Rating Curve= 0 ,0
Exp/Cntr=0.3,0.1

Type RM Length L Ch R = 1 ,2318    ,867,867,867
BEGIN DESCRIPTION:
BYRNES CREEK 4.0
END DESCRIPTION:
XS GIS Cut Line= 3
      2826755.68      10236853.1       2826662.5       10236370.
      2826955.68     10236053.12
#Sta/Elev= 30
    4508  1027.9  4533.9 1024.11  4590.9  1021.2  4599.6  1020.2  4630.2  1012.5
  4780.6  998.13  4803.4  994.74  4833.9  993.15  4884.8  987.81  4925.5  989.38
  4935.7  989.25  4953.9  986.49    4959  987.47  4982.4  980.96  4986.6  980.22
  4995.1  975.83  4995.6  975.33  5019.5  975.83  5035.7  978.92  5042.5   978.2
  5070.8  979.71  5077.6  978.78  5091.8  980.33  5113.3   985.3  5120.2  985.14
  5127.5  988.18  5141.7  989.73    5191  990.58  5353.8 1002.31  5431.7 1003.74
#Mann= 5 ,-1 , 0
    4508     .12       0  4780.6     .05       0  4982.4     .12       0
  4995.1     .07       0  5019.5     .12       0
Bank Sta=4995.1,5019.5
XS Rating Curve= 0 ,0
Exp/Cntr=0.3,0.1

Type RM Length L Ch R = 1 ,1451    ,759,759,759
BEGIN DESCRIPTION:
Mapping XS 62da9729
END DESCRIPTION:
XS GIS Cut Line= 3
      2826598.25     10237201.77      2827492.64     10236579.13
      2827785.61     10235982.34
#Sta/Elev= 30
    4140 1042.05  4359.4 1041.69  4475.5 1037.27  4511.2 1032.76  4526.1    1033
  4588.9 1026.49  4612.1 1025.63    4705 1014.23  4746.8 1011.79  4819.2 1001.45
  4904.8   992.5  4934.5  988.02  4949.3  982.62  4955.4  983.18  4964.2  979.46
  4970.3  978.65  4977.6  974.72  4985.1  973.38  4987.8  971.33  4988.3  970.83
  5012.2  971.33  5035.7  973.78  5077.6  985.55  5217.3   998.6  5250.6 1001.95
  5325.6 1003.79  5430.5 1002.61  5481.6 1000.08  5638.5 1001.01  5894.6  1009.3
#Mann= 4 ,-1 , 0
    4140     .05       0  4987.8     .07       0  5012.2     .05       0
  5217.3     .05       0
Bank Sta=4987.8,5012.2
XS Rating Curve= 0 ,0
Exp/Cntr=0.3,0.1

Type RM Length L Ch R = 1 ,692     ,0,0,0
BEGIN DESCRIPTION:
BYRNES CREEK 1.0
END DESCRIPTION:
XS GIS Cut Line= 3
      2827805.67     10237003.15      2827934.75       10236616.
      2828005.68     10236203.15
#Sta/Elev= 30
  4591.9  991.04  4602.5  992.95    4613  991.75  4634.1  996.54  4639.4  993.91
  4686.8 1000.44  4734.2 1000.76  4760.6  997.54  4765.8  999.62  4772.7  997.28
  4792.2   993.4  4797.5  995.14  4813.3  992.11  4860.7  990.64  4874.8  987.84
  4918.7  978.45  4923.9  981.44  4929.3  977.61  4950.3  972.58  4955.6  974.98
  4986.6   964.9  4987.1   964.4  5011.1   964.9  5023.2  977.67  5031.7   983.2
  5036.7  981.67    5074  988.96  5133.2   993.4  5373.5 1006.27  5418.9 1008.06
#Mann= 7 ,-1 , 0
  4591.9     .12       0  4772.7     .05       0  4874.8     .12       0
  4986.6     .07       0  5011.1     .12       0  5133.2     .05       0
  5373.5     .12       0
Bank Sta=4986.6,5011.1
XS Rating Curve= 0 ,0
Exp/Cntr=0.3,0.1

Chan Stop Cuts=-1
Use User Specified Reach Order=0
Composite Channel Slope=5