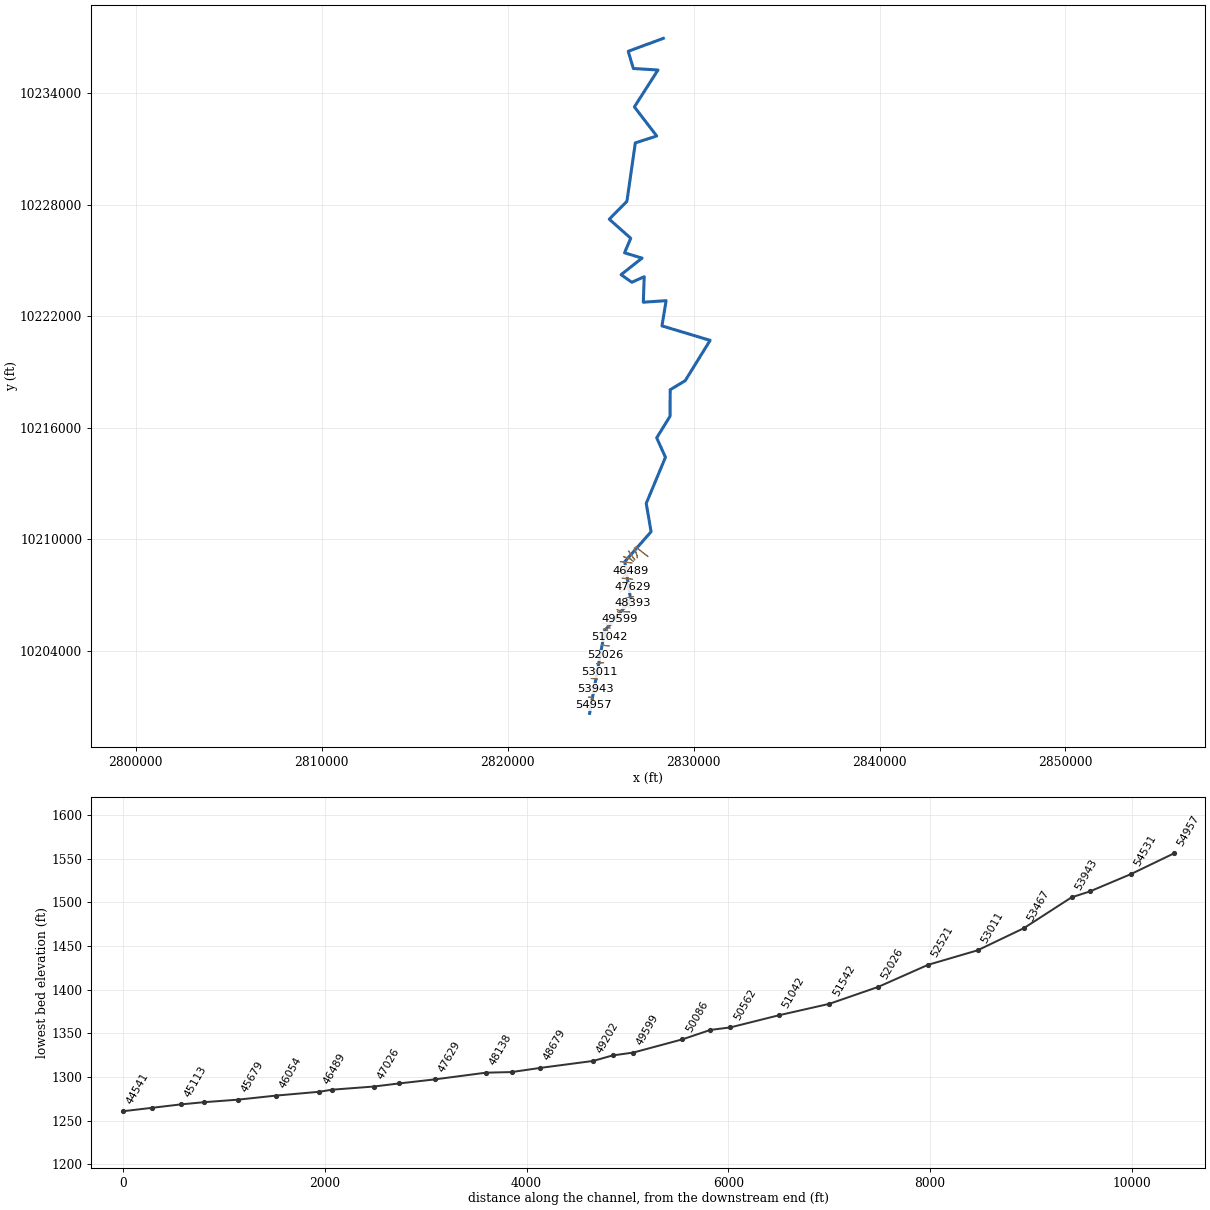
--- BYRNES CREEK.prj (project) ---

Proj Title=BYRNES CREEK Base Level Engineering
Current Plan=p01
Default Exp/Contr=0.3,0.1
English Units
Geom File=g01
Flow File=f01
Plan File=p01
BEGIN DESCRIPTION:
BYRNES CREEK
END DESCRIPTION:

--- BYRNES CREEK.p01 (plan) ---

Plan Title=Multiple Run
Short Identifier=Multiple
Geom File=g01
Flow File=f01
Subcritical Flow
K Sum by GR= 0
Std Step Tol= 0.01
Critical Tol= 0.01
Num of Std Step Trials= 20
Max Error Tol= 0.3
Flow Tol Ratio= 0.001
Split Flow NTrial= 30
Split Flow Tol= 0.02
Split Flow Ratio= 0.02
Log Output Level= 0
Friction Slope Method= 1
Unsteady Friction Slope Method= 2
Unsteady Bridges Friction Slope Method= 1
Parabolic Critical Depth
Global Vel Dist=  1 , 1 , 1
Global Log Level= 0
CheckData=True
Encroach Param= -1, 0, 0, 0
BEGIN DESCRIPTION:
Multiple Run
END DESCRIPTION:

--- BYRNES CREEK.f01 (steady flow) ---

Flow Title=Multiple
Number of Profiles=7
Profile Names=10-year,25-year,50-year,1pct_min,100-year,1pct_plu,500-year
River Rch & RM= BYRNES CREEK,Reach-1,54957
     223     348     784     651    1101    1860    1654
River Rch & RM= BYRNES CREEK,Reach-1,48679
     537     897    1673    1179    2371    4771    3493
River Rch & RM= BYRNES CREEK,Reach-1,37043
     701    1186    2336    1666    3346    6718    4908
River Rch & RM= BYRNES CREEK,Reach-1,35233
    1005    1725    3808    2819    5544   10903    8094
River Rch & RM= BYRNES CREEK,Reach-1,34301
    1706    3034    6485    4598    9545   19813   13781
River Rch & RM= BYRNES CREEK,Reach-1,22625
    1751    3121    6612    4659    9733   20335   14046
River Rch & RM= BYRNES CREEK,Reach-1,21498
    2228    4035    8473    5866   12546   26832   18030
River Rch & RM= BYRNES CREEK,Reach-1,13857
    3427    6402   12907    8919   19136   41057   26983
River Rch & RM= BYRNES CREEK,Reach-1,9621
    3912    7369   14407    9805   21334   46418   29912
River Rch & RM= BYRNES CREEK,Reach-1,5147
    4389    8319   15957   10707   23627   52136   33009
Boundary for River Rch & Prof#=BYRNES CREEK,Reach-1,1
Up Type=0
Dn Type=3
Dn Slope=0.005
Boundary for River Rch & Prof#=BYRNES CREEK,Reach-1,2
Up Type=0
Dn Type=3
Dn Slope=0.005
Boundary for River Rch & Prof#=BYRNES CREEK,Reach-1,3
Up Type=0
Dn Type=3
Dn Slope=0.005
Boundary for River Rch & Prof#=BYRNES CREEK,Reach-1,4
Up Type=0
Dn Type=3
Dn Slope=0.005
Boundary for River Rch & Prof#=BYRNES CREEK,Reach-1,5
Up Type=0
Dn Type=3
Dn Slope=0.005
Boundary for River Rch & Prof#=BYRNES CREEK,Reach-1,6
Up Type=0
Dn Type=3
Dn Slope=0.005
Boundary for River Rch & Prof#=BYRNES CREEK,Reach-1,7
Up Type=0
Dn Type=3
Dn Slope=0.005

--- BYRNES CREEK.g01 (geometry) ---

Geom Title=Existing Conditions

River Reach=BYRNES CREEK,Reach-1
Reach XY= 30
      2824409.00     10200626.00      2825224.25     10205076.00
      2826621.25     10206726.00      2826302.50     10208792.00
      2827715.75     10210401.00      2827455.75     10211925.00
      2828488.75     10214406.00      2828018.25     10215452.00
      2828736.25     10216616.00      2828743.25     10218040.00
      2829550.00     10218527.00      2830890.25     10220697.00
      2828300.50     10221477.00      2828524.25     10222833.00
      2827298.75     10222751.00      2827346.50     10224121.00
      2826681.25     10223824.00      2826102.75     10224230.00
      2827230.00     10225123.00      2826290.25     10225409.00
      2826621.25     10226192.00      2825468.75     10227218.00
      2826415.25     10228177.00      2826869.50     10231322.00
      2828019.25     10231694.00      2826818.75     10233260.00
      2828087.50     10235245.00      2826763.25     10235326.00
      2826486.75     10236251.00      2828376.75     10236949.00

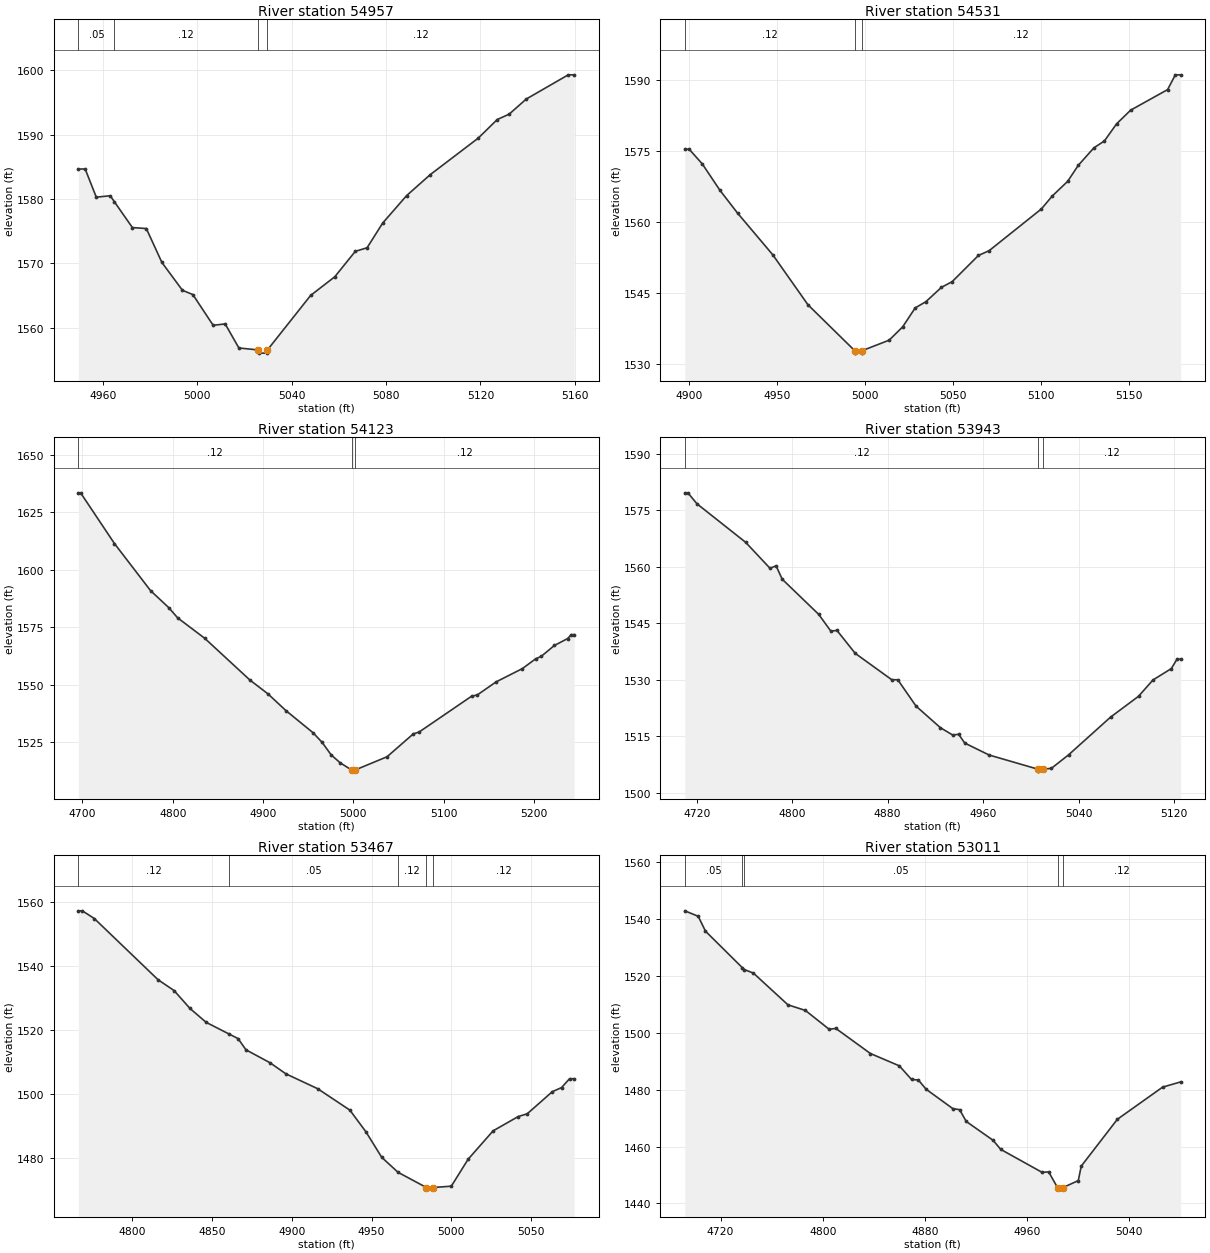
Type RM Length L Ch R = 1,54957,426,426,426
BEGIN DESCRIPTION:
BYRNES CREEK 101.0
END DESCRIPTION:
XS GIS Cut Line= 3
      2824405.72     10201053.14      2824448.25     10201080.00
      2824605.67     10201053.11
#Sta/Elev= 30
  4949.7 1584.66  4952.6 1584.66  4957.3 1580.28  4963.2 1580.50  4965.0 1579.55
  4972.6 1575.55  4978.5 1575.40  4985.1 1570.12  4993.8 1565.79  4998.2 1565.13
  5006.8 1560.35  5011.9 1560.56  5017.7 1556.82  5025.8 1556.52  5026.1 1556.02
  5029.6 1556.02  5029.8 1556.52  5048.1 1565.00  5058.3 1567.89  5067.0 1571.85
  5072.0 1572.41  5078.6 1576.25  5088.7 1580.51  5098.8 1583.80  5119.1 1589.47
  5127.1 1592.35  5132.2 1593.20  5139.4 1595.54  5157.2 1599.31  5159.7 1599.31
#Mann=4,-1,0
  4949.7    0.05       0  4965.0    0.12       0  5025.8    0.07       0
  5029.8    0.12       0
Bank Sta=5025.8,5029.8
Exp/Cntr=0.3,0.1

Type RM Length L Ch R = 1,54531,408,408,408
BEGIN DESCRIPTION:
BYRNES CREEK 100.0
END DESCRIPTION:
XS GIS Cut Line= 3
      2824355.72     10201503.11      2824458.00     10201505.00
      2824605.67     10201403.12
#Sta/Elev= 30
  4897.7 1575.46  4900.2 1575.46  4907.7 1572.32  4917.7 1566.75  4927.7 1561.93
  4947.7 1553.11  4967.7 1542.53  4994.3 1532.81  4994.6 1532.31  4998.1 1532.31
  4998.3 1532.81  5013.8 1535.05  5021.5 1537.88  5028.6 1541.88  5034.7 1543.20
  5043.5 1546.23  5049.6 1547.43  5064.5 1552.97  5070.6 1553.99  5100.3 1562.82
  5106.5 1565.57  5115.2 1568.65  5121.3 1572.07  5130.1 1575.74  5136.1 1577.21
  5143.0 1580.82  5151.0 1583.72  5172.0 1588.07  5176.4 1591.20  5179.4 1591.20
#Mann=3,-1,0
  4897.7    0.12       0  4994.3    0.07       0  4998.3    0.12       0
Bank Sta=4994.3,4998.3
Exp/Cntr=0.3,0.1

Type RM Length L Ch R = 1,54123,180,180,180
BEGIN DESCRIPTION:
BYRNES CREEK 99.0
END DESCRIPTION:
XS GIS Cut Line= 3
      2824255.67     10201903.11      2824560.25     10201900.00
      2824755.70     10201753.10
#Sta/Elev= 30
  4695.4 1633.39  4697.9 1633.39  4735.4 1611.35  4775.4 1590.87  4795.4 1583.53
  4805.4 1579.04  4835.4 1570.15  4885.4 1552.02  4905.4 1546.00  4925.4 1538.70
  4955.4 1529.09  4965.4 1524.91  4975.4 1519.48  4985.4 1516.03  4998.0 1512.92
  4998.2 1512.42  5002.0 1512.92  5037.3 1518.67  5066.4 1528.62  5072.7 1529.39
  5131.0 1545.01  5137.2 1545.53  5158.1 1551.22  5187.2 1557.00  5201.8 1561.22
  5208.0 1562.29  5222.6 1567.04  5237.2 1570.03  5241.4 1571.74  5244.5 1571.74
#Mann=3,-1,0
  4695.4    0.12       0  4998.0    0.07       0  5002.0    0.12       0
Bank Sta=4998,5002
Exp/Cntr=0.3,0.1

Type RM Length L Ch R = 1,53943,476,476,476
BEGIN DESCRIPTION:
BYRNES CREEK 98.0
END DESCRIPTION:
XS GIS Cut Line= 3
      2824355.64     10202003.10      2824640.00     10202060.00
      2824705.71     10201953.08
#Sta/Elev= 30
  4710.0 1579.59  4712.6 1579.59  4720.2 1576.68  4761.0 1566.45  4781.4 1559.56
  4786.5 1560.22  4791.6 1556.67  4822.2 1547.33  4832.4 1542.87  4837.5 1543.07
  4852.8 1536.98  4883.4 1529.98  4888.5 1529.96  4903.8 1522.96  4924.2 1517.24
  4934.4 1515.31  4939.5 1515.48  4944.6 1513.16  4965.0 1509.99  5006.1 1506.21
  5006.3 1505.71  5010.1 1506.21  5017.2 1506.45  5031.6 1510.03  5066.8 1520.05
  5090.2 1525.57  5102.3 1529.90  5117.7 1532.93  5122.5 1535.44  5125.5 1535.44
#Mann=3,-1,0
  4710.0    0.12       0  5006.1    0.07       0  5010.1    0.12       0
Bank Sta=5006.1,5010.1
Exp/Cntr=0.3,0.1

Type RM Length L Ch R = 1,53467,456,456,456
BEGIN DESCRIPTION:
BYRNES CREEK 97.0
END DESCRIPTION:
XS GIS Cut Line= 3
      2824505.71     10202503.11      2824739.25     10202492.00
      2824805.70     10202453.10
#Sta/Elev= 30
  4766.2 1557.20  4768.7 1557.20  4776.2 1554.80  4816.2 1535.65  4826.2 1532.29
  4836.2 1526.68  4846.3 1522.35  4860.5 1518.74  4866.3 1517.27  4871.3 1513.75
  4886.3 1509.73  4896.3 1506.25  4916.3 1501.58  4936.4 1494.91  4946.4 1488.18
  4956.4 1480.14  4966.6 1475.47  4984.4 1470.71  4984.7 1470.21  4988.2 1470.21
  4988.4 1470.71  5000.0 1471.13  5010.5 1479.53  5026.2 1488.43  5041.9 1492.89
  5047.6 1493.76  5063.3 1500.67  5069.1 1501.95  5074.1 1504.71  5077.0 1504.71
#Mann=5,-1,0
  4766.2    0.12       0  4860.5    0.05       0  4966.6    0.12       0
  4984.4    0.07       0  4988.4    0.12       0
Bank Sta=4984.4,4988.4
Exp/Cntr=0.3,0.1

Type RM Length L Ch R = 1,53011,490,490,490
BEGIN DESCRIPTION:
BYRNES CREEK 96.0
END DESCRIPTION:
XS GIS Cut Line= 3
      2824605.66     10203003.12      2824899.25     10202910.00
      2824955.66     10202853.13
#Sta/Elev= 30
  4692.0 1542.86  4702.5 1540.94  4708.2 1535.70  4737.0 1522.89  4738.5 1522.23
  4745.7 1520.97  4772.7 1509.83  4786.4 1507.84  4805.0 1501.22  4810.2 1501.53
  4837.3 1492.70  4859.9 1488.37  4869.5 1483.57  4874.8 1483.40  4880.9 1480.14
  4901.8 1473.33  4907.1 1472.97  4912.3 1468.82  4933.3 1462.20  4939.3 1459.00
  4971.6 1450.94  4976.8 1451.09  4983.8 1445.53  4984.0 1445.03  4987.8 1445.53
  5000.0 1448.03  5002.3 1453.11  5030.6 1469.59  5066.0 1480.88  5080.1 1482.72
#Mann=5,-1,0
  4692.0    0.05       0  4737.0    0.12       0  4738.5    0.05       0
  4983.8    0.07       0  4987.8    0.12       0
Bank Sta=4983.8,4987.8
Exp/Cntr=0.3,0.1

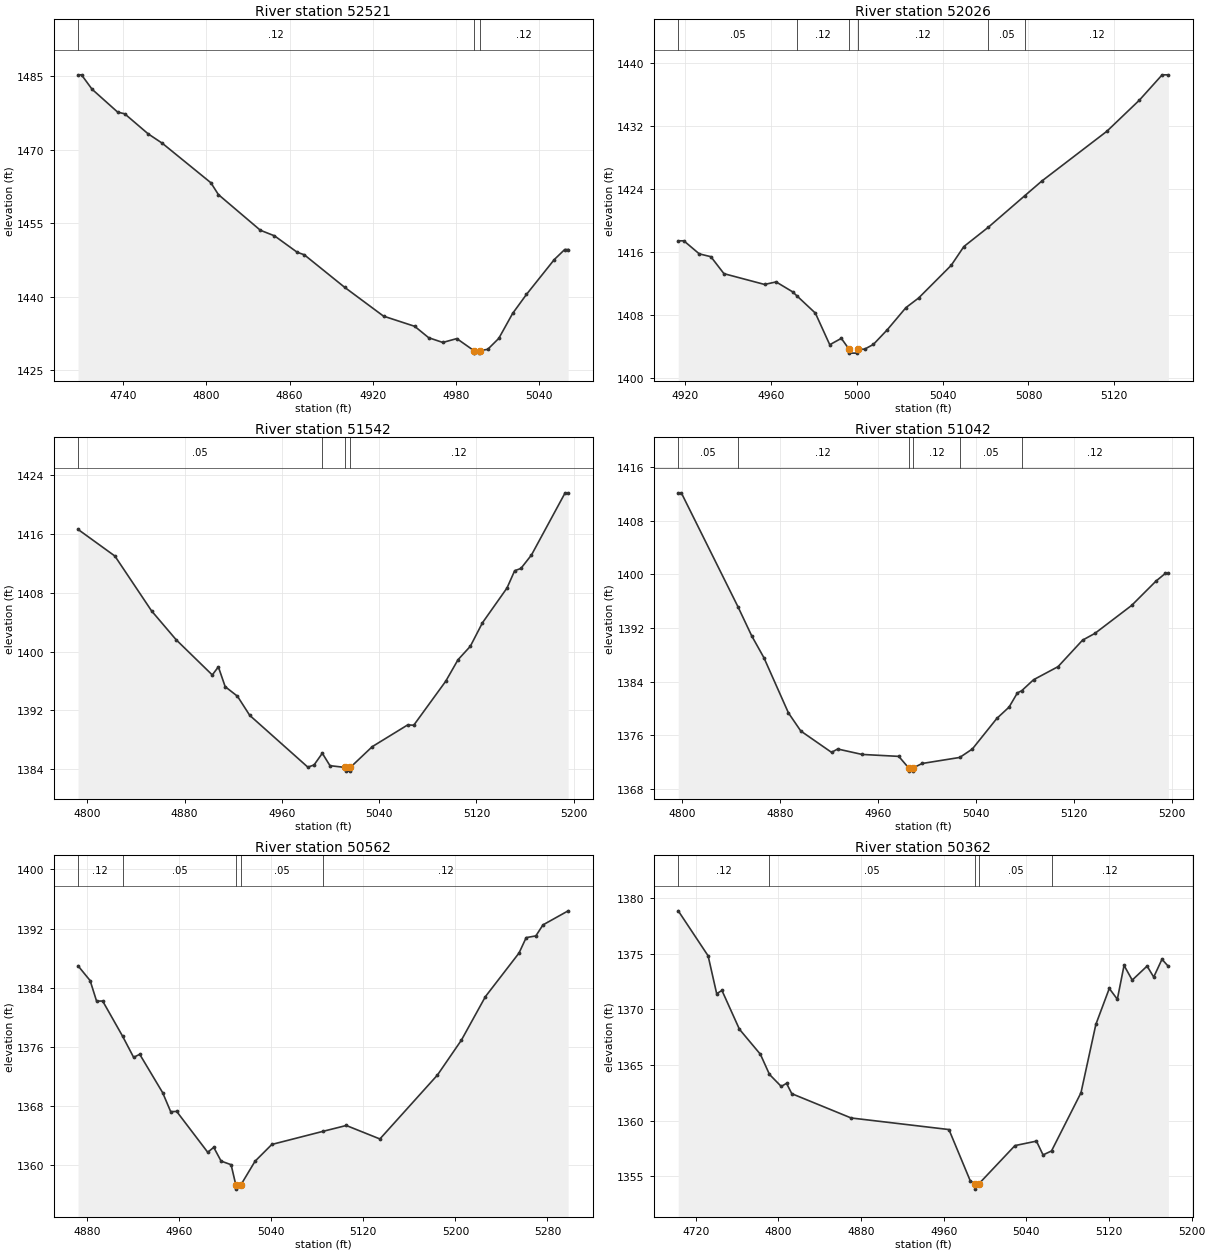
Type RM Length L Ch R = 1,52521,495,495,495
BEGIN DESCRIPTION:
BYRNES CREEK 95.0
END DESCRIPTION:
XS GIS Cut Line= 3
      2824805.67     10203303.11      2825094.75     10203349.00
      2825155.71     10203353.11
#Sta/Elev= 30
  4707.3 1485.32  4709.8 1485.32  4717.4 1482.38  4735.9 1477.70  4741.0 1477.35
  4757.9 1473.26  4768.1 1471.34  4803.2 1463.26  4808.6 1460.85  4838.9 1453.56
  4849.1 1452.42  4865.5 1449.06  4870.6 1448.55  4899.7 1441.91  4927.8 1436.01
  4950.3 1433.93  4960.4 1431.60  4970.6 1430.63  4980.7 1431.42  4993.1 1428.95
  4993.4 1428.45  4996.9 1428.45  4997.1 1428.95  5003.0 1429.22  5011.0 1431.46
  5021.0 1436.56  5031.0 1440.45  5051.1 1447.58  5058.6 1449.62  5061.1 1449.62
#Mann=3,-1,0
  4707.3    0.12       0  4993.1    0.07       0  4997.1    0.12       0
Bank Sta=4993.1,4997.1
Exp/Cntr=0.3,0.1

Type RM Length L Ch R = 1,52026,484,484,484
BEGIN DESCRIPTION:
BYRNES CREEK 94.0
END DESCRIPTION:
XS GIS Cut Line= 3
      2825055.72     10203803.13      2825133.75     10203832.00
      2825255.66     10203753.13
#Sta/Elev= 30
  4916.8 1417.41  4919.4 1417.41  4926.6 1415.75  4932.0 1415.39  4938.1 1413.23
  4957.0 1411.86  4962.4 1412.18  4970.1 1410.92  4972.2 1410.38  4980.7 1408.21
  4987.4 1404.19  4992.8 1405.00  4996.4 1403.62  4996.6 1403.12  5000.1 1403.12
  5000.4 1403.62  5003.6 1403.62  5007.7 1404.22  5014.2 1406.09  5022.9 1408.91
  5028.8 1410.13  5044.0 1414.29  5049.9 1416.68  5061.3 1419.14  5078.2 1423.13
  5086.2 1425.01  5116.5 1431.34  5131.7 1435.31  5142.3 1438.53  5145.2 1438.53
#Mann=6,-1,0
  4916.8    0.05       0  4972.2    0.12       0  4996.4    0.07       0
  5000.4    0.12       0  5061.3    0.05       0  5078.2    0.12       0
Bank Sta=4996.4,5000.4
Exp/Cntr=0.3,0.1

Type RM Length L Ch R = 1,51542,500,500,500
BEGIN DESCRIPTION:
BYRNES CREEK 93.0
END DESCRIPTION:
XS GIS Cut Line= 3
      2825055.68     10204303.11      2825261.50     10204276.00
      2825455.66     10204253.11
#Sta/Elev= 30
  4792.4 1416.61  4822.7 1412.99  4852.9 1405.53  4873.1 1401.61  4902.8 1396.83
  4907.8 1397.93  4913.4 1395.24  4923.5 1393.94  4933.6 1391.34  4981.4 1384.30
  4986.5 1384.60  4993.3 1386.19  4999.6 1384.50  5012.3 1384.26  5012.5 1383.76
  5016.0 1383.76  5016.3 1384.26  5034.4 1387.09  5063.5 1390.04  5068.5 1390.00
  5094.8 1395.98  5104.9 1398.90  5115.0 1400.72  5125.0 1403.92  5145.2 1408.65
  5151.5 1411.00  5156.6 1411.30  5165.3 1413.13  5193.0 1421.58  5195.5 1421.58
#Mann=4,-1,0
  4792.4    0.05       0  4993.3    0.12       0  5012.3    0.07       0
  5016.3    0.12       0
Bank Sta=5012.3,5016.3
Exp/Cntr=0.3,0.1

Type RM Length L Ch R = 1,51042,480,480,480
BEGIN DESCRIPTION:
BYRNES CREEK 92.0
END DESCRIPTION:
XS GIS Cut Line= 3
      2825055.71     10204753.11      2825258.75     10204745.00
      2825455.68     10204753.11
#Sta/Elev= 30
  4796.8 1412.16  4799.3 1412.16  4845.6 1395.16  4856.8 1390.83  4866.8 1387.56
  4886.8 1379.34  4896.9 1376.64  4922.0 1373.46  4927.0 1373.96  4946.9 1373.15
  4976.9 1372.86  4984.9 1371.16  4985.2 1370.66  4988.7 1370.66  4988.9 1371.16
  4996.0 1371.80  5026.7 1372.70  5037.0 1373.96  5057.0 1378.52  5067.0 1380.21
  5073.8 1382.33  5077.3 1382.65  5087.0 1384.29  5107.0 1386.24  5127.0 1390.19
  5137.1 1391.20  5167.1 1395.37  5187.1 1399.02  5194.6 1400.14  5197.1 1400.14
#Mann=6,-1,0
  4796.8    0.05       0  4845.6    0.12       0  4984.9    0.07       0
  4988.9    0.12       0  5026.7    0.05       0  5077.3    0.12       0
Bank Sta=4984.9,4988.9
Exp/Cntr=0.3,0.1

Type RM Length L Ch R = 1,50562,200,200,200
BEGIN DESCRIPTION:
BYRNES CREEK 91.0
END DESCRIPTION:
XS GIS Cut Line= 3
      2825155.66     10205153.10      2825277.50     10205192.00
      2825455.67     10204953.13
#Sta/Elev= 30
  4872.1 1386.97  4882.6 1384.97  4888.2 1382.20  4893.5 1382.21  4910.9 1377.43
  4920.4 1374.60  4925.7 1375.01  4945.6 1369.83  4952.6 1367.26  4957.8 1367.29
  4984.8 1361.77  4990.0 1362.44  4996.4 1360.58  5005.1 1360.09  5009.3 1357.29
  5009.6 1356.79  5013.3 1357.29  5025.9 1360.56  5040.5 1362.83  5084.7 1364.59
  5105.2 1365.39  5134.4 1363.57  5184.4 1372.21  5205.2 1376.92  5226.1 1382.81
  5255.3 1388.70  5261.5 1390.78  5269.9 1391.01  5276.1 1392.50  5298.0 1394.40
#Mann=5,-1,0
  4872.1    0.12       0  4910.9    0.05       0  5009.3    0.05       0
  5013.3    0.05       0  5084.7    0.12       0
Bank Sta=5009.3,5013.3
Exp/Cntr=0.3,0.1

Type RM Length L Ch R = 1,50362,276,276,276
BEGIN DESCRIPTION:
Mapping XS 420cb1ab
END DESCRIPTION:
XS GIS Cut Line= 3
      2825137.17     10205474.40      2825316.62     10205446.16
      2825500.90     10205218.70
#Sta/Elev= 30
  4703.0 1378.84  4731.9 1374.80  4740.2 1371.40  4745.3 1371.69  4762.2 1368.21
  4782.5 1365.96  4791.3 1364.15  4802.7 1363.07  4807.8 1363.35  4812.9 1362.42
  4870.3 1360.24  4965.0 1359.20  4985.8 1354.56  4990.2 1354.35  4990.5 1353.85
  4994.2 1354.35  5028.9 1357.76  5049.7 1358.16  5056.1 1356.92  5064.3 1357.28
  5092.8 1362.50  5107.2 1368.64  5120.2 1371.87  5128.0 1370.90  5134.5 1373.94
  5142.4 1372.62  5156.8 1373.88  5163.2 1372.89  5171.2 1374.49  5177.4 1373.85
#Mann=5,-1,0
  4703.0    0.12       0  4791.3    0.05       0  4990.2    0.05       0
  4994.2    0.05       0  5064.3    0.12       0
Bank Sta=4990.2,4994.2
Exp/Cntr=0.3,0.1

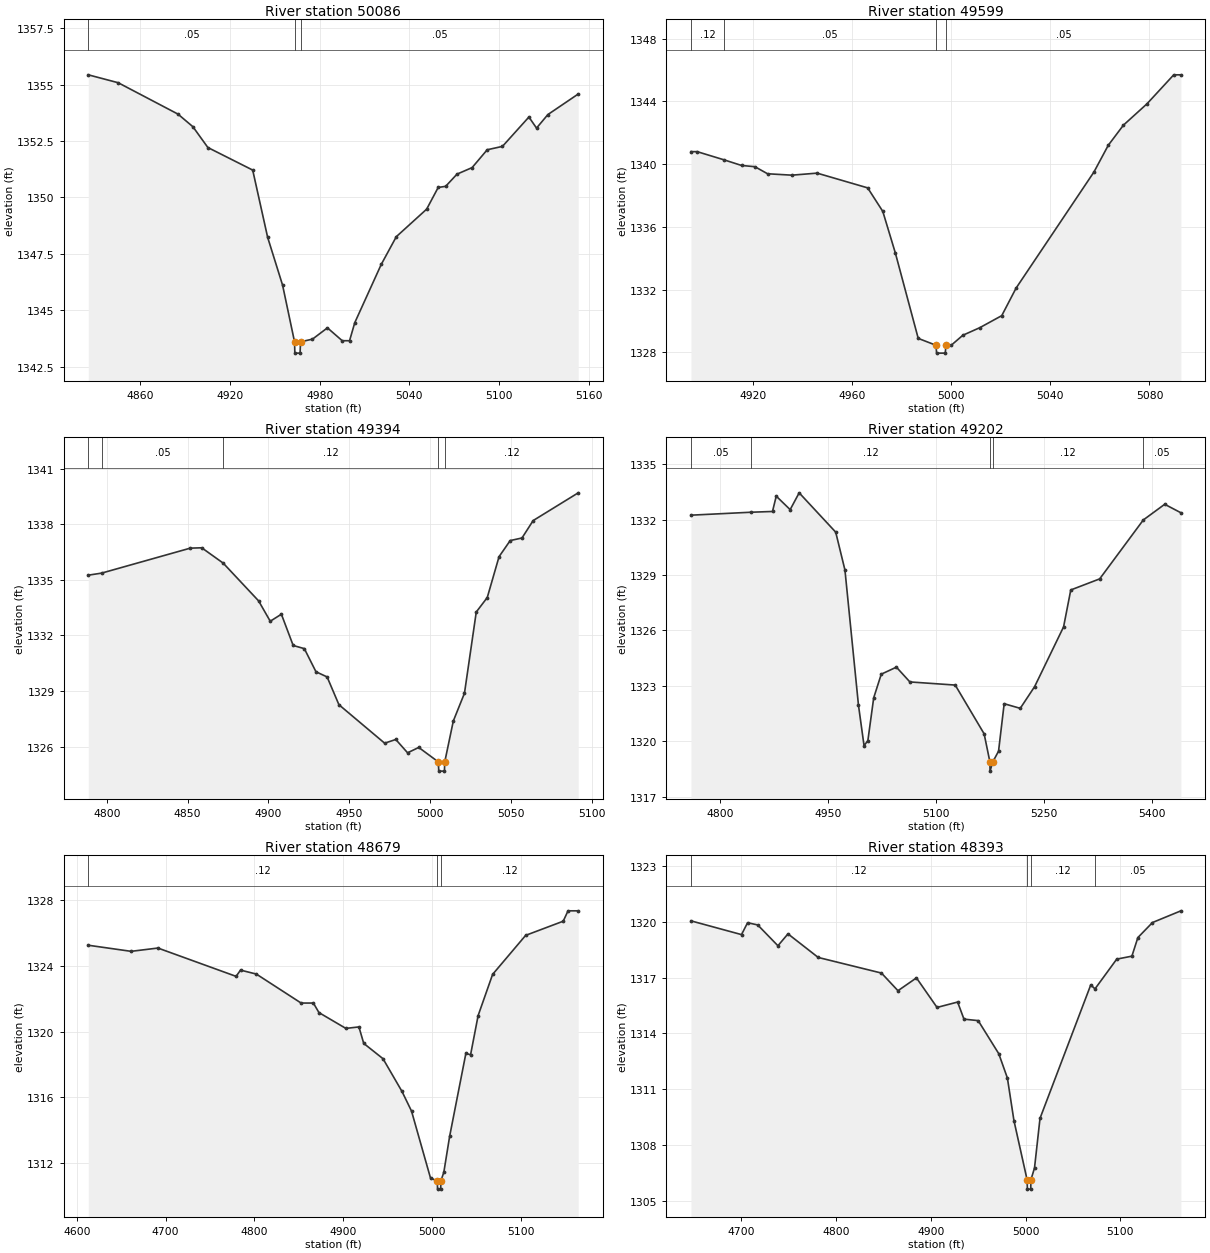
Type RM Length L Ch R = 1,50086,487,487,487
BEGIN DESCRIPTION:
BYRNES CREEK 90.0
END DESCRIPTION:
XS GIS Cut Line= 3
      2825405.70     10205553.11      2825580.50     10205554.00
      2825605.69     10205403.09
#Sta/Elev= 30
  4825.2 1355.43  4845.2 1355.08  4885.2 1353.69  4895.2 1353.13  4905.2 1352.21
  4935.2 1351.21  4945.2 1348.23  4955.2 1346.11  4963.2 1343.60  4963.4 1343.10
  4966.9 1343.10  4967.2 1343.60  4975.2 1343.72  4985.2 1344.22  4995.1 1343.65
  5000.0 1343.65  5003.5 1344.45  5021.2 1347.03  5031.3 1348.26  5051.6 1349.48
  5059.3 1350.44  5064.3 1350.49  5071.9 1351.03  5082.0 1351.32  5092.1 1352.11
  5102.3 1352.26  5120.0 1353.56  5125.1 1353.07  5132.7 1353.67  5153.0 1354.58
#Mann=3,-1,0
  4825.2    0.05       0  4963.2    0.05       0  4967.2    0.05       0
Bank Sta=4963.2,4967.2
Exp/Cntr=0.3,0.1

Type RM Length L Ch R = 1,49599,205,205,205
BEGIN DESCRIPTION:
BYRNES CREEK 89.0
END DESCRIPTION:
XS GIS Cut Line= 3
      2825855.69     10205803.11      2825958.75     10205783.00
      2826005.71     10205703.07
#Sta/Elev= 27
  4895.0 1340.80  4897.5 1340.80  4908.3 1340.28  4915.4 1339.92  4920.8 1339.84
  4925.9 1339.39  4935.7 1339.30  4945.9 1339.43  4966.3 1338.49  4972.4 1336.99
  4977.5 1334.32  4986.7 1328.89  4993.9 1328.45  4994.1 1327.95  4997.6 1327.95
  4997.9 1328.45  5000.0 1328.45  5004.7 1329.09  5011.5 1329.57  5020.4 1330.34
  5026.2 1332.10  5057.6 1339.50  5063.4 1341.21  5069.5 1342.49  5079.0 1343.85
  5089.8 1345.70  5092.7 1345.70
#Mann=4,-1,0
  4895.0    0.12       0  4908.3    0.05       0  4993.9    0.05       0
  4997.9    0.05       0
Bank Sta=4993.9,4997.9
Exp/Cntr=0.3,0.1

Type RM Length L Ch R = 1,49394,192,192,192
BEGIN DESCRIPTION:
Mapping XS 6c605a8a
END DESCRIPTION:
XS GIS Cut Line= 2
      2825929.86     10206086.45      2826150.12     10205878.09
#Sta/Elev= 30
  4788.5 1335.26  4796.7 1335.37  4851.6 1336.72  4858.7 1336.74  4872.0 1335.91
  4893.9 1333.87  4901.1 1332.77  4908.0 1333.15  4915.3 1331.46  4922.2 1331.29
  4929.4 1330.04  4936.3 1329.76  4943.6 1328.26  4971.9 1326.18  4978.8 1326.38
  4986.1 1325.66  4993.0 1325.95  5005.1 1325.17  5005.4 1324.67  5008.9 1324.67
  5009.1 1325.17  5014.4 1327.38  5021.3 1328.88  5028.6 1333.27  5035.4 1334.05
  5042.7 1336.26  5049.6 1337.13  5056.9 1337.27  5063.8 1338.21  5091.7 1339.71
#Mann=5,-1,0
  4788.5    0.12       0  4796.7    0.05       0  4872.0    0.12       0
  5005.1    0.07       0  5009.1    0.12       0
Bank Sta=5005.1,5009.1
Exp/Cntr=0.3,0.1

Type RM Length L Ch R = 1,49202,523,523,523
BEGIN DESCRIPTION:
BYRNES CREEK 88.0
END DESCRIPTION:
XS GIS Cut Line= 3
      2825894.96     10206204.06      2826192.51     10206105.98
      2826558.18     10206082.71
#Sta/Elev= 30
  4759.9 1332.24  4843.4 1332.40  4873.0 1332.44  4878.2 1333.27  4897.5 1332.54
  4910.0 1333.45  4960.7 1331.32  4973.5 1329.27  4992.3 1321.94  5000.0 1319.76
  5005.3 1320.03  5013.4 1322.35  5023.9 1323.63  5044.9 1324.01  5063.6 1323.21
  5126.5 1323.04  5166.6 1320.40  5174.6 1318.88  5174.8 1318.38  5178.6 1318.88
  5186.6 1319.46  5194.4 1322.03  5216.7 1321.78  5236.7 1322.96  5276.8 1326.19
  5286.8 1328.19  5326.9 1328.79  5387.4 1331.98  5417.1 1332.83  5439.6 1332.37
#Mann=5,-1,0
  4759.9    0.05       0  4843.4    0.12       0  5174.6    0.07       0
  5178.6    0.12       0  5387.4    0.05       0
Bank Sta=5174.6,5178.6
Exp/Cntr=0.3,0.1

Type RM Length L Ch R = 1,48679,286,286,286
BEGIN DESCRIPTION:
BYRNES CREEK 87.0
END DESCRIPTION:
XS GIS Cut Line= 3
      2826067.83     10206448.37      2826370.35     10206411.80
      2826601.03     10206323.84
#Sta/Elev= 30
  4612.9 1325.24  4661.1 1324.87  4691.3 1325.07  4779.3 1323.35  4784.3 1323.73
  4802.1 1323.49  4852.5 1321.73  4866.3 1321.73  4872.6 1321.15  4902.9 1320.19
  4917.6 1320.28  4923.0 1319.28  4944.7 1318.35  4966.1 1316.36  4976.8 1315.17
  4998.2 1311.10  5005.9 1310.93  5006.1 1310.43  5009.6 1310.43  5009.9 1310.93
  5013.2 1311.46  5019.7 1313.63  5038.0 1318.67  5043.3 1318.59  5051.8 1320.97
  5068.1 1323.47  5105.3 1325.84  5147.6 1326.70  5153.0 1327.33  5164.5 1327.33
#Mann=3,-1,0
  4612.9    0.12       0  5005.9    0.07       0  5009.9    0.12       0
Bank Sta=5005.9,5009.9
Exp/Cntr=0.3,0.1

Type RM Length L Ch R = 1,48393,255,255,255
BEGIN DESCRIPTION:
Mapping XS 87d03e2c
END DESCRIPTION:
XS GIS Cut Line= 3
      2826259.54     10206620.31      2826468.66     10206696.35
      2826725.32     10206552.57
#Sta/Elev= 30
  4647.1 1320.06  4700.4 1319.32  4706.8 1319.96  4717.5 1319.84  4738.8 1318.72
  4749.4 1319.36  4781.3 1318.09  4848.0 1317.25  4865.4 1316.30  4884.9 1316.99
  4906.6 1315.40  4928.3 1315.69  4935.0 1314.77  4950.0 1314.69  4971.7 1312.91
  4980.8 1311.60  4987.7 1309.31  5001.6 1306.12  5001.9 1305.62  5005.4 1305.62
  5005.6 1306.12  5009.4 1306.76  5015.2 1309.43  5068.7 1316.61  5073.2 1316.40
  5096.1 1318.00  5112.1 1318.16  5118.4 1319.16  5133.8 1319.97  5163.8 1320.60
#Mann=4,-1,0
  4647.1    0.12       0  5001.6    0.07       0  5005.6    0.12       0
  5073.2    0.05       0
Bank Sta=5001.6,5005.6
Exp/Cntr=0.3,0.1

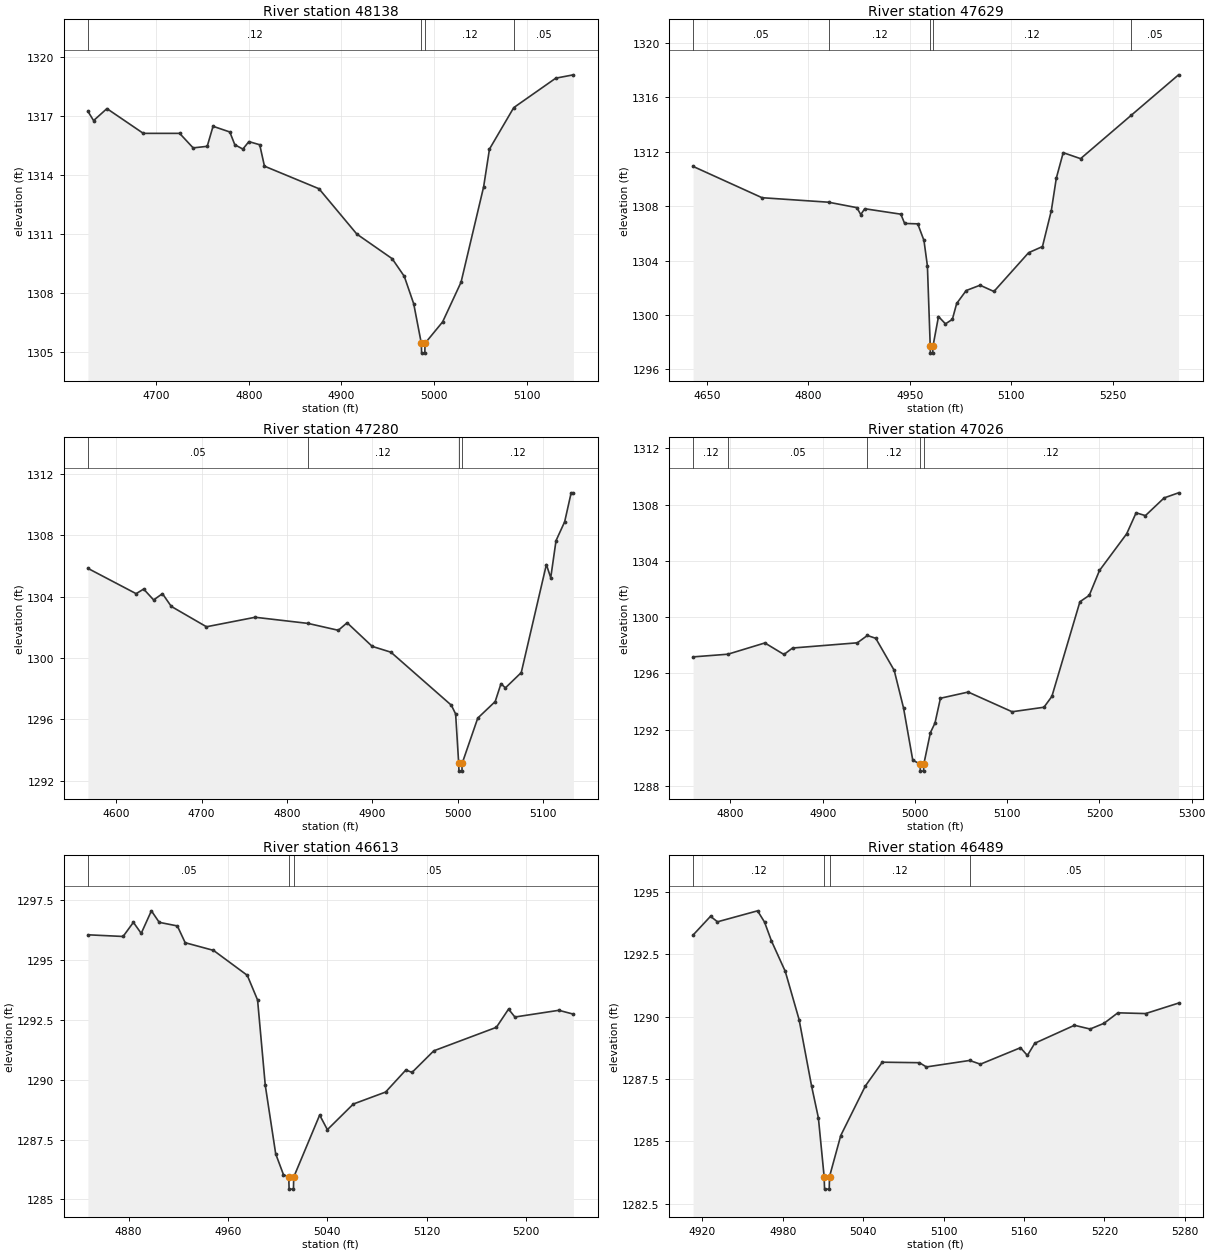
Type RM Length L Ch R = 1,48138,509,509,509
BEGIN DESCRIPTION:
BYRNES CREEK 86.0
END DESCRIPTION:
XS GIS Cut Line= 3
      2826250.02     10206771.21      2826412.82     10206835.37
      2826754.24     10206908.74
#Sta/Elev= 30
  4626.4 1317.23  4632.5 1316.76  4646.9 1317.37  4686.2 1316.11  4725.4 1316.11
  4740.0 1315.37  4755.2 1315.45  4761.5 1316.47  4779.6 1316.18  4785.0 1315.53
  4793.7 1315.31  4800.2 1315.69  4811.9 1315.53  4817.0 1314.44  4875.9 1313.29
  4916.8 1310.98  4954.9 1309.73  4968.0 1308.83  4978.2 1307.43  4986.4 1305.42
  4986.7 1304.92  4990.2 1304.92  4990.4 1305.42  5009.4 1306.51  5029.3 1308.53
  5053.7 1313.39  5060.0 1315.31  5086.2 1317.42  5131.6 1318.92  5150.6 1319.09
#Mann=4,-1,0
  4626.4    0.12       0  4986.4    0.07       0  4990.4    0.12       0
  5086.2    0.05       0
Bank Sta=4986.4,4990.4
Exp/Cntr=0.3,0.1

Type RM Length L Ch R = 1,47629,349,349,349
BEGIN DESCRIPTION:
BYRNES CREEK 85.0
END DESCRIPTION:
XS GIS Cut Line= 3
      2826054.32     10207156.78      2826330.34     10207311.72
      2826722.10     10207399.93
#Sta/Elev= 30
  4629.3 1310.92  4731.3 1308.62  4829.6 1308.29  4871.6 1307.89  4877.3 1307.38
  4883.2 1307.81  4936.6 1307.41  4942.2 1306.73  4961.6 1306.70  4970.8 1305.48
  4975.9 1303.61  4980.1 1297.70  4980.3 1297.20  4983.8 1297.20  4984.1 1297.70
  4992.3 1299.89  5002.6 1299.35  5012.8 1299.68  5019.2 1300.85  5033.3 1301.80
  5053.8 1302.19  5074.3 1301.73  5125.6 1304.58  5146.1 1305.03  5159.2 1307.67
  5166.6 1310.06  5176.8 1311.93  5202.5 1311.49  5277.7 1314.69  5347.4 1317.65
#Mann=5,-1,0
  4629.3    0.05       0  4829.6    0.12       0  4980.1    0.07       0
  4984.1    0.12       0  5277.7    0.05       0
Bank Sta=4980.1,4984.1
Exp/Cntr=0.3,0.1

Type RM Length L Ch R = 1,47280,254,254,254
BEGIN DESCRIPTION:
BYRNES CREEK 84.0
END DESCRIPTION:
XS GIS Cut Line= 3
      2826000.91     10207531.84      2826327.74     10207611.20
      2826555.69     10207653.11
#Sta/Elev= 30
  4567.1 1305.85  4623.5 1304.20  4632.3 1304.50  4644.0 1303.79  4654.3 1304.20
  4664.6 1303.37  4705.8 1302.04  4762.8 1302.66  4824.6 1302.26  4860.1 1301.81
  4870.4 1302.30  4899.8 1300.76  4921.7 1300.38  4992.4 1296.92  4997.4 1296.35
  5001.0 1293.12  5001.3 1292.62  5004.8 1292.62  5005.0 1293.12  5023.3 1296.08
  5043.7 1297.16  5050.5 1298.33  5055.6 1298.05  5074.2 1299.05  5103.6 1306.10
  5108.7 1305.24  5114.9 1307.66  5125.0 1308.89  5132.6 1310.78  5135.2 1310.78
#Mann=4,-1,0
  4567.1    0.05       0  4824.6    0.12       0  5001.0    0.07       0
  5005.0    0.12       0
Bank Sta=5001,5005
Exp/Cntr=0.3,0.1

Type RM Length L Ch R = 1,47026,413,413,413
BEGIN DESCRIPTION:
BYRNES CREEK 83.0
END DESCRIPTION:
XS GIS Cut Line= 3
      2826178.03     10207893.75      2826525.66     10207872.91
      2826701.08     10207843.03
#Sta/Elev= 30
  4759.6 1297.17  4797.3 1297.36  4837.4 1298.16  4858.1 1297.34  4867.4 1297.80
  4937.6 1298.17  4948.5 1298.69  4957.6 1298.49  4977.6 1296.21  4987.7 1293.54
  4997.7 1289.83  5005.7 1289.55  5005.9 1289.05  5009.4 1289.05  5009.7 1289.55
  5016.8 1291.78  5021.8 1292.47  5027.7 1294.23  5057.8 1294.67  5105.4 1293.27
  5139.9 1293.59  5148.5 1294.36  5178.9 1301.09  5189.0 1301.54  5200.1 1303.31
  5229.6 1305.92  5239.8 1307.41  5249.9 1307.21  5270.2 1308.47  5285.8 1308.83
#Mann=5,-1,0
  4759.6    0.12       0  4797.3    0.05       0  4948.5    0.12       0
  5005.7    0.07       0  5009.7    0.12       0
Bank Sta=5005.7,5009.7
Exp/Cntr=0.3,0.1

Type RM Length L Ch R = 1,46613,124,124,124
BEGIN DESCRIPTION:
Mapping XS fd11a5f1
END DESCRIPTION:
XS GIS Cut Line= 3
      2826254.83     10208013.55      2826443.62     10208155.47
      2826597.26     10208173.69
#Sta/Elev= 30
  4847.2 1296.04  4875.5 1295.97  4883.8 1296.56  4890.1 1296.10  4898.3 1297.04
  4904.6 1296.56  4919.2 1296.41  4925.5 1295.71  4948.3 1295.39  4975.5 1294.35
  4983.8 1293.32  4990.0 1289.76  4998.4 1286.90  5004.6 1286.04  5008.9 1285.93
  5009.2 1285.43  5012.7 1285.43  5012.9 1285.93  5033.8 1288.52  5040.0 1287.91
  5060.9 1288.98  5086.9 1289.48  5103.2 1290.40  5108.2 1290.30  5125.7 1291.20
  5176.1 1292.18  5185.9 1292.94  5191.0 1292.61  5226.4 1292.89  5238.1 1292.73
#Mann=3,-1,0
  4847.2    0.05       0  5008.9    0.05       0  5012.9    0.05       0
Bank Sta=5008.9,5012.9
Exp/Cntr=0.3,0.1

Type RM Length L Ch R = 1,46489,435,435,435
BEGIN DESCRIPTION:
Mapping XS 2e83e365
END DESCRIPTION:
XS GIS Cut Line= 2
      2826239.17     10208194.52      2826589.47     10208286.98
#Sta/Elev= 30
  4913.0 1293.27  4926.0 1294.02  4931.2 1293.80  4961.1 1294.24  4966.3 1293.79
  4971.5 1293.03  4981.8 1291.81  4992.1 1289.88  5001.4 1287.22  5006.5 1285.94
  5010.8 1283.58  5011.1 1283.08  5014.6 1283.08  5014.8 1283.58  5023.2 1285.23
  5041.6 1287.22  5054.2 1288.17  5081.9 1288.15  5087.1 1287.98  5119.4 1288.24
  5127.4 1288.09  5157.3 1288.75  5162.5 1288.44  5168.0 1288.93  5197.6 1289.65
  5209.3 1289.50  5219.7 1289.73  5230.0 1290.15  5250.7 1290.12  5275.3 1290.54
#Mann=4,-1,0
  4913.0    0.12       0  5010.8    0.07       0  5014.8    0.12       0
  5119.4    0.05       0
Bank Sta=5010.8,5014.8
Exp/Cntr=0.3,0.1

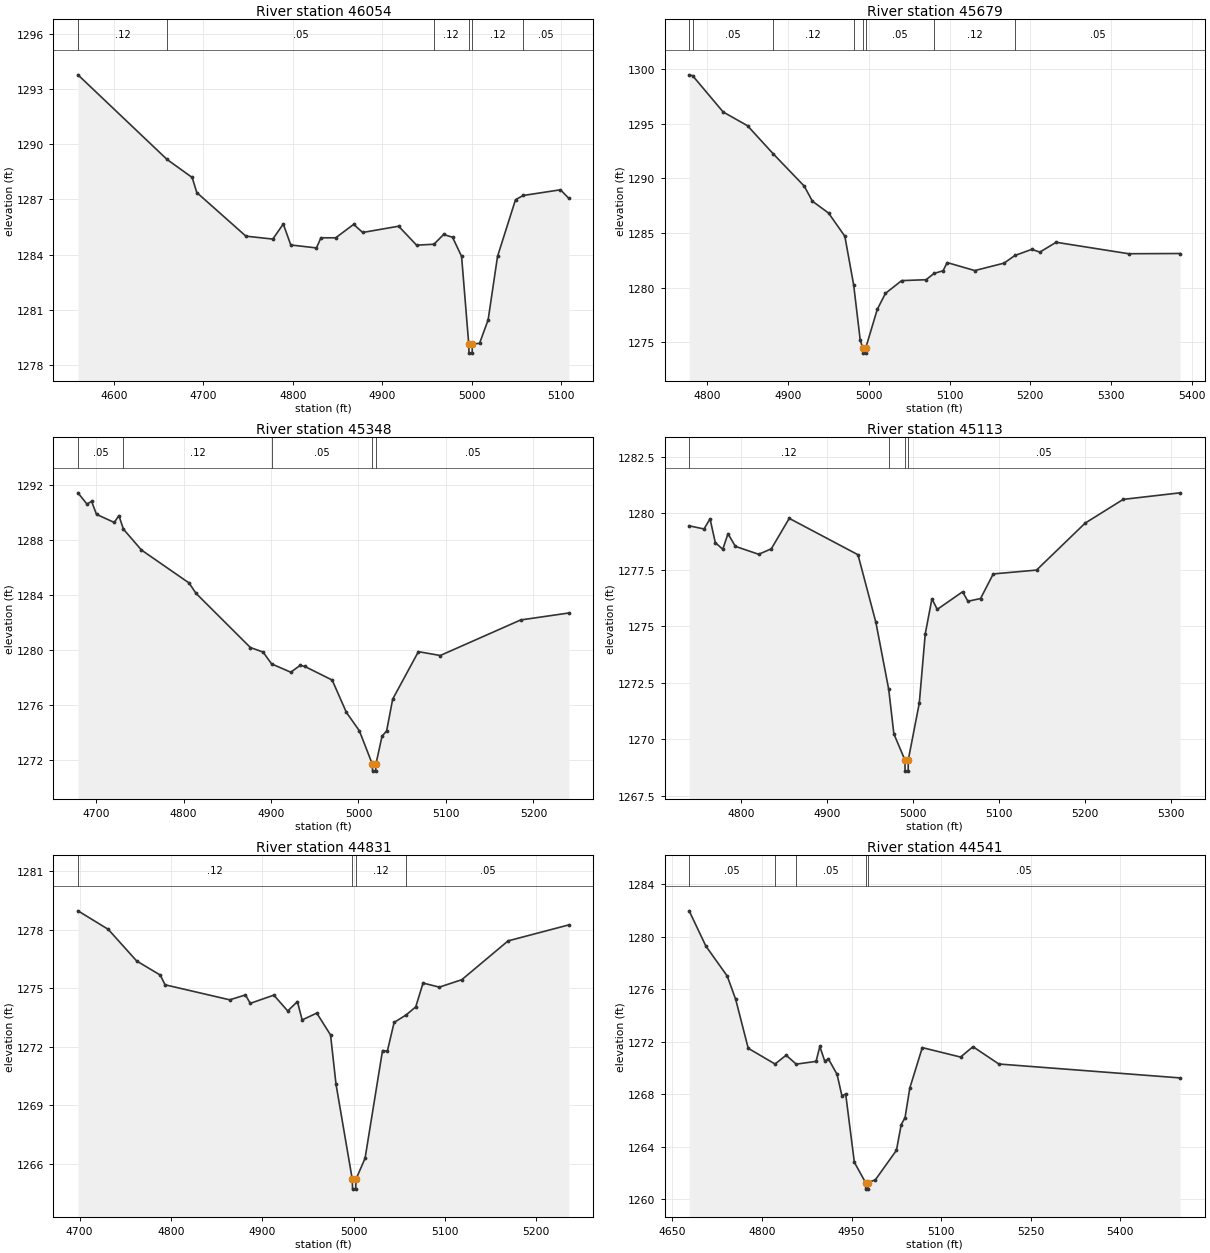
Type RM Length L Ch R = 1,46054,375,375,375
BEGIN DESCRIPTION:
BYRNES CREEK 82.0
END DESCRIPTION:
XS GIS Cut Line= 3
      2826088.19     10208546.09      2826317.39     10208532.33
      2826635.05     10208499.21
#Sta/Elev= 30
  4559.8 1293.77  4659.4 1289.17  4687.5 1288.19  4692.7 1287.37  4747.6 1285.00
  4777.7 1284.84  4789.4 1285.66  4797.8 1284.52  4826.5 1284.36  4831.5 1284.91
  4848.0 1284.91  4868.1 1285.64  4878.2 1285.20  4918.4 1285.54  4938.5 1284.51
  4957.9 1284.56  4968.7 1285.09  4978.7 1284.94  4988.8 1283.90  4996.8 1279.14
  4997.1 1278.64  5000.6 1278.64  5000.8 1279.14  5008.9 1279.17  5018.5 1280.45
  5029.0 1283.90  5049.1 1286.98  5057.6 1287.21  5099.4 1287.52  5108.8 1287.05
#Mann=6,-1,0
  4559.8    0.12       0  4659.4    0.05       0  4957.9    0.12       0
  4996.8    0.07       0  5000.8    0.12       0  5057.6    0.05       0
Bank Sta=4996.8,5000.8
Exp/Cntr=0.3,0.1

Type RM Length L Ch R = 1,45679,331,331,331
BEGIN DESCRIPTION:
Mapping XS 7326d3df
END DESCRIPTION:
XS GIS Cut Line= 3
      2826073.84     10208790.88      2826392.84     10208757.03
      2826678.02     10208720.57
#Sta/Elev= 30
  4777.4 1299.48  4781.7 1299.40  4819.5 1296.08  4849.7 1294.82  4881.4 1292.26
  4920.0 1289.29  4930.1 1287.91  4950.2 1286.82  4970.3 1284.70  4981.2 1280.26
  4989.3 1275.23  4992.3 1274.50  4992.6 1274.00  4996.1 1274.00  4996.3 1274.50
  5010.5 1278.01  5020.6 1279.47  5040.7 1280.64  5070.9 1280.72  5080.9 1281.30
  5092.0 1281.54  5097.1 1282.29  5131.3 1281.56  5167.6 1282.24  5181.0 1282.94
  5201.9 1283.50  5212.0 1283.25  5232.1 1284.15  5322.0 1283.10  5385.7 1283.12
#Mann=8,-1,0
  4777.4    0.12       0  4781.7    0.05       0  4881.4    0.12       0
  4981.2    0.05       0  4992.3    0.05       0  4996.3    0.05       0
  5080.9    0.12       0  5181.0    0.05       0
Bank Sta=4992.3,4996.3
Exp/Cntr=0.3,0.1

Type RM Length L Ch R = 1,45348,235,235,235
BEGIN DESCRIPTION:
BYRNES CREEK 81.0
END DESCRIPTION:
XS GIS Cut Line= 3
      2826255.66     10209053.12      2826626.42     10208924.69
      2826751.01     10208810.47
#Sta/Elev= 30
  4679.2 1291.45  4689.5 1290.63  4694.8 1290.83  4700.4 1289.88  4720.7 1289.29
  4726.0 1289.79  4731.2 1288.80  4751.8 1287.28  4806.2 1284.88  4814.1 1284.13
  4876.4 1280.17  4890.9 1279.84  4900.6 1278.98  4922.6 1278.37  4933.2 1278.87
  4938.7 1278.79  4969.9 1277.80  4986.1 1275.45  5001.0 1274.10  5015.9 1271.66
  5016.1 1271.16  5019.6 1271.16  5019.9 1271.66  5026.9 1273.70  5032.2 1274.10
  5039.1 1276.41  5068.5 1279.87  5093.5 1279.59  5185.4 1282.18  5240.6 1282.69
#Mann=5,-1,0
  4679.2    0.05       0  4731.2    0.12       0  4900.6    0.05       0
  5015.9    0.05       0  5019.9    0.05       0
Bank Sta=5015.9,5019.9
Exp/Cntr=0.3,0.1

Type RM Length L Ch R = 1,45113,282,282,282
BEGIN DESCRIPTION:
Mapping XS f8371afb
END DESCRIPTION:
XS GIS Cut Line= 2
      2826506.15     10209357.25      2826836.85     10208891.15
#Sta/Elev= 30
  4739.6 1279.44  4756.9 1279.30  4763.9 1279.75  4770.0 1278.70  4778.7 1278.40
  4784.8 1279.09  4793.4 1278.53  4820.5 1278.18  4835.2 1278.42  4856.1 1279.77
  4936.1 1278.16  4957.0 1275.16  4971.9 1272.20  4977.9 1270.23  4990.7 1269.08
  4991.0 1268.58  4994.5 1268.58  4994.7 1269.08  5007.5 1271.59  5014.4 1274.65
  5022.2 1276.21  5028.4 1275.74  5057.9 1276.52  5064.1 1276.10  5078.8 1276.22
  5093.6 1277.31  5144.0 1277.48  5200.6 1279.56  5244.9 1280.61  5311.1 1280.90
#Mann=4,-1,0
  4739.6    0.12       0  4971.9    0.05       0  4990.7    0.05       0
  4994.7    0.05       0
Bank Sta=4990.7,4994.7
Exp/Cntr=0.3,0.1

Type RM Length L Ch R = 1,44831,290,290,290
BEGIN DESCRIPTION:
BYRNES CREEK 80.0
END DESCRIPTION:
XS GIS Cut Line= 3
      2826819.94     10209520.02      2826960.47     10209116.49
      2826973.43     10209006.96
#Sta/Elev= 30
  4698.2 1278.96  4731.4 1278.01  4762.5 1276.39  4788.3 1275.67  4793.6 1275.17
  4864.4 1274.40  4881.6 1274.65  4886.9 1274.22  4912.7 1274.64  4927.9 1273.83
  4938.5 1274.31  4943.7 1273.37  4959.7 1273.72  4974.8 1272.60  4980.8 1270.07
  4998.6 1265.20  4998.9 1264.70  5002.4 1264.70  5002.6 1265.20  5012.6 1266.28
  5031.7 1271.80  5037.0 1271.77  5044.4 1273.24  5057.7 1273.63  5068.1 1274.04
  5076.1 1275.26  5093.9 1275.05  5118.5 1275.43  5169.2 1277.42  5235.8 1278.24
#Mann=4,-1,0
  4698.2    0.12       0  4998.6    0.07       0  5002.6    0.12       0
  5057.7    0.05       0
Bank Sta=4998.6,5002.6
Exp/Cntr=0.3,0.1

Type RM Length L Ch R = 1,44541,101,101,101
BEGIN DESCRIPTION:
BYRNES CREEK 79.0
END DESCRIPTION:
XS GIS Cut Line= 3
      2826914.58     10209601.81      2827039.61     10209466.36
      2827539.65     10209070.49
#Sta/Elev= 30
  4678.0 1281.99  4706.0 1279.30  4741.7 1277.02  4755.9 1275.24  4776.9 1271.51
  4821.8 1270.31  4840.4 1270.98  4857.3 1270.30  4890.5 1270.51  4896.8 1271.65
  4904.9 1270.55  4911.3 1270.69  4925.7 1269.52  4933.8 1267.88  4940.1 1268.02
  4954.6 1262.82  4973.4 1261.27  4973.6 1260.77  4977.1 1260.77  4977.4 1261.27
  4989.8 1261.48  5025.1 1263.73  5033.1 1265.69  5039.5 1266.22  5047.5 1268.48
  5068.4 1271.56  5132.5 1270.84  5153.3 1271.63  5196.6 1270.31  5500.1 1269.25
#Mann=5,-1,0
  4678.0    0.05       0  4821.8    0.12       0  4857.3    0.05       0
  4973.4    0.03       0  4977.4    0.05       0
Bank Sta=4973.4,4977.4
Exp/Cntr=0.3,0.1