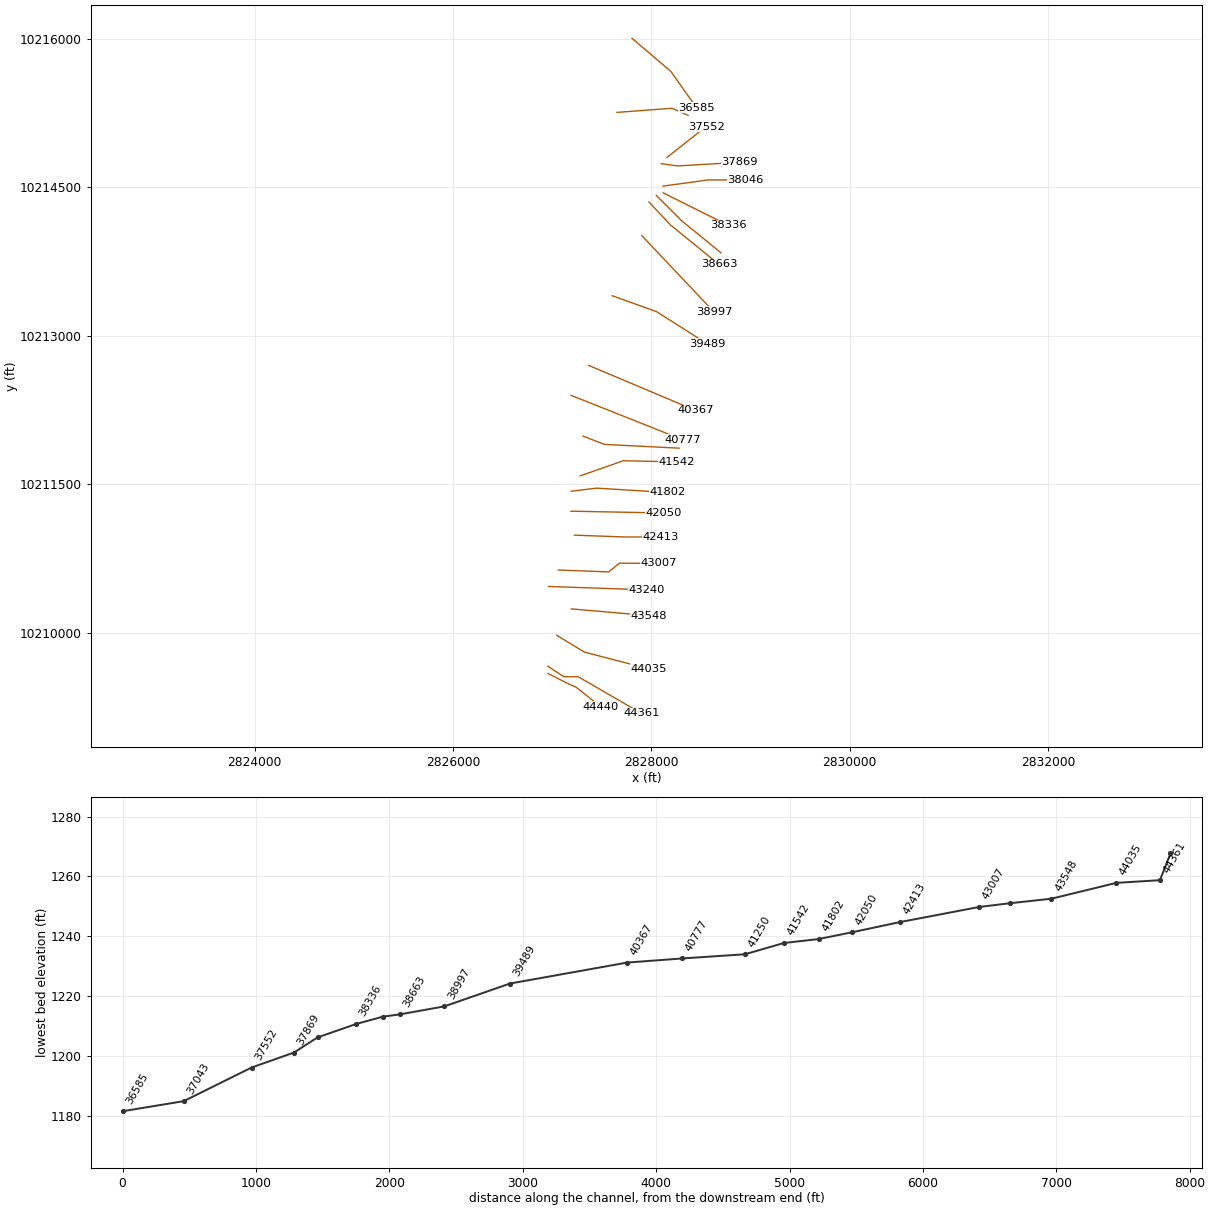
HEC-RAS study BYRNES CREEK.prj: BYRNES CREEK Base Level Engineering

--- BYRNES CREEK.g01 (geometry) --- (continued)

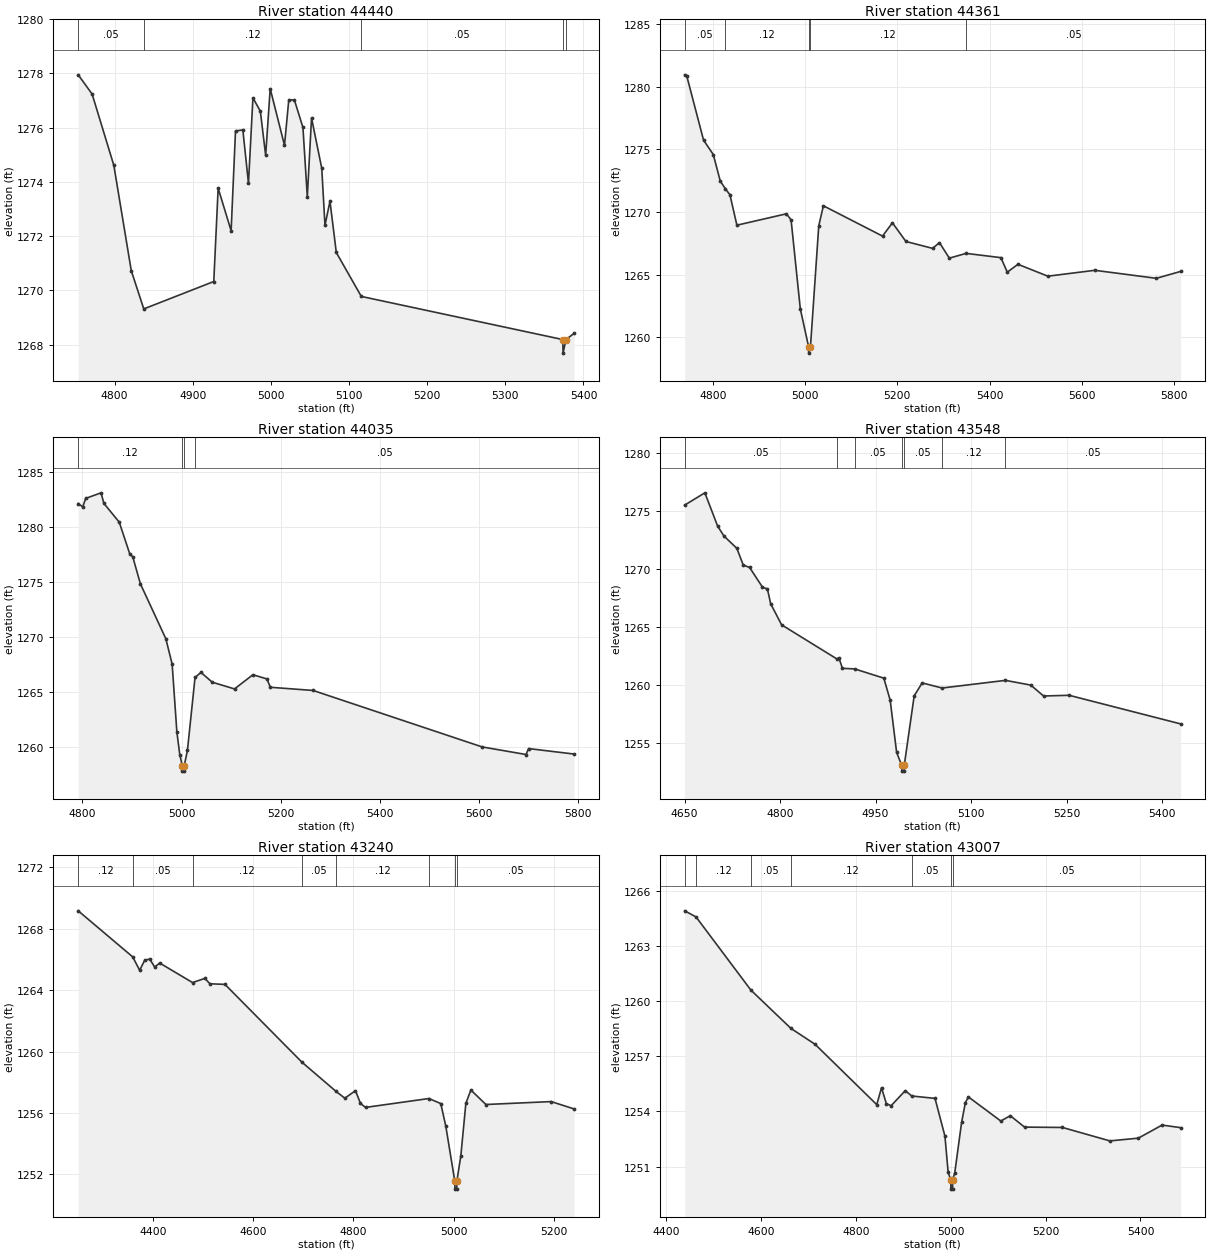
Type RM Length L Ch R = 1,44440,79,79,79
BEGIN DESCRIPTION:
Mapping XS dc0e6323
END DESCRIPTION:
XS GIS Cut Line= 4
      2826957.96     10209587.75      2827172.79     10209478.38
      2827237.90     10209451.04      2827491.89     10209251.47
#Sta/Elev= 30
  4753.4 1277.95  4771.2 1277.24  4799.0 1274.61  4821.3 1270.73  4837.3 1269.32
  4926.9 1270.33  4932.5 1273.77  4949.1 1272.20  4954.7 1275.88  4964.1 1275.92
  4971.3 1273.95  4977.0 1277.10  4986.5 1276.61  4993.3 1274.98  4999.1 1277.44
  5017.4 1275.35  5022.9 1277.03  5030.1 1277.02  5041.0 1276.01  5046.6 1273.45
  5052.0 1276.36  5065.1 1274.50  5069.2 1272.40  5075.6 1273.29  5083.7 1271.40
  5115.7 1269.78  5373.6 1268.19  5373.9 1267.69  5377.6 1268.19  5388.1 1268.42
#Mann=5,-1,0
  4753.4    0.05       0  4837.3    0.12       0  5115.7    0.05       0
  5373.6    0.07       0  5377.6    0.05       0
Bank Sta=5373.6,5377.6
Exp/Cntr=0.3,0.1

Type RM Length L Ch R = 1,44361,326,326,326
BEGIN DESCRIPTION:
BYRNES CREEK 78.0
END DESCRIPTION:
XS GIS Cut Line= 4
      2826956.63     10209660.69      2827116.80     10209555.21
      2827263.94     10209553.90      2827900.72     10209184.31
#Sta/Elev= 30
  4738.9 1280.94  4743.7 1280.81  4779.8 1275.73  4800.9 1274.58  4816.0 1272.47
  4826.8 1271.86  4837.0 1271.37  4852.1 1268.94  4959.6 1269.85  4969.6 1269.36
  4989.6 1262.26  5007.6 1259.23  5007.8 1258.73  5011.6 1259.23  5029.6 1268.89
  5039.6 1270.49  5167.8 1268.07  5189.3 1269.13  5218.6 1267.64  5276.4 1267.09
  5291.2 1267.55  5312.7 1266.31  5349.0 1266.69  5424.5 1266.35  5438.3 1265.19
  5461.4 1265.82  5526.3 1264.87  5628.1 1265.34  5761.5 1264.70  5814.1 1265.25
#Mann=5,-1,0
  4738.9    0.05       0  4826.8    0.12       0  5007.6    0.07       0
  5011.6    0.12       0  5349.0    0.05       0
Bank Sta=5007.6,5011.6
Exp/Cntr=0.3,0.1

Type RM Length L Ch R = 1,44035,487,487,487
BEGIN DESCRIPTION:
Mapping XS 4998bb02
END DESCRIPTION:
XS GIS Cut Line= 3
      2827044.75     10209974.04      2827324.27     10209803.90
      2827975.28     10209633.77
#Sta/Elev= 30
  4791.5 1282.16  4800.7 1281.85  4806.5 1282.62  4837.5 1283.13  4843.3 1282.17
  4874.3 1280.46  4895.6 1277.56  4901.4 1277.33  4916.9 1274.86  4968.2 1269.87
  4980.9 1267.57  4990.5 1261.37  4996.3 1259.35  5001.3 1258.34  5001.6 1257.84
  5005.1 1257.84  5005.3 1258.34  5011.8 1259.74  5027.1 1266.35  5039.0 1266.81
  5061.8 1265.92  5106.7 1265.31  5143.8 1266.60  5171.9 1266.22  5179.1 1265.46
  5265.2 1265.17  5606.0 1260.04  5694.6 1259.35  5699.7 1259.89  5791.6 1259.39
#Mann=4,-1,0
  4791.5    0.12       0  5001.3    0.07       0  5005.3    0.12       0
  5027.1    0.05       0
Bank Sta=5001.3,5005.3
Exp/Cntr=0.3,0.1

Type RM Length L Ch R = 1,43548,308,308,308
BEGIN DESCRIPTION:
Mapping XS 561c4de4
END DESCRIPTION:
XS GIS Cut Line= 2
      2827194.08     10210239.67      2827970.13     10210171.96
#Sta/Elev= 30
  4650.2 1275.52  4681.9 1276.58  4702.0 1273.70  4712.0 1272.84  4732.1 1271.79
  4742.2 1270.34  4752.2 1270.13  4772.3 1268.44  4780.2 1268.27  4785.2 1267.01
  4802.4 1265.18  4888.7 1262.25  4892.7 1262.28  4898.0 1261.42  4917.2 1261.37
  4963.0 1260.57  4973.0 1258.67  4983.1 1254.16  4991.1 1253.04  4991.4 1252.54
  4994.9 1252.54  4995.1 1253.04  5010.7 1259.04  5023.2 1260.16  5054.6 1259.72
  5154.1 1260.38  5193.9 1259.97  5213.9 1259.03  5254.1 1259.09  5429.2 1256.62
#Mann=7,-1,0
  4650.2    0.05       0  4888.7    0.12       0  4917.2    0.05       0
  4991.1    0.05       0  4995.1    0.05       0  5054.6    0.12       0
  5154.1    0.05       0
Bank Sta=4991.1,4995.1
Exp/Cntr=0.3,0.1

Type RM Length L Ch R = 1,43240,233,233,233
BEGIN DESCRIPTION:
Mapping XS 27461ba5
END DESCRIPTION:
XS GIS Cut Line= 2
      2826963.25     10210466.36      2827951.48     10210432.67
#Sta/Elev= 30
  4251.4 1269.16  4360.1 1266.16  4373.9 1265.29  4383.9 1265.94  4393.9 1266.02
  4403.9 1265.50  4413.9 1265.76  4479.3 1264.49  4504.0 1264.76  4514.0 1264.41
  4544.0 1264.37  4697.3 1259.31  4765.2 1257.41  4783.0 1256.96  4804.2 1257.45
  4814.2 1256.62  4824.2 1256.36  4950.6 1256.94  4974.3 1256.61  4984.3 1255.14
  5002.3 1251.54  5002.5 1251.04  5006.0 1251.04  5006.3 1251.54  5014.3 1253.22
  5024.3 1256.63  5034.3 1257.49  5064.3 1256.55  5194.4 1256.74  5240.2 1256.26
#Mann=8,-1,0
  4251.4    0.12       0  4360.1    0.05       0  4479.3    0.12       0
  4697.3    0.05       0  4765.2    0.12       0  4950.6    0.05       0
  5002.3    0.05       0  5006.3    0.05       0
Bank Sta=5002.3,5006.3
Exp/Cntr=0.3,0.1

Type RM Length L Ch R = 1,43007,594,594,594
BEGIN DESCRIPTION:
Mapping XS 896c8bc9
END DESCRIPTION:
XS GIS Cut Line= 4
      2827060.93     10210632.51      2827569.59     10210613.41
      2827678.97     10210701.95      2828074.81     10210698.48
#Sta/Elev= 30
  4439.1 1264.90  4463.0 1264.57  4578.8 1260.59  4663.2 1258.51  4714.0 1257.65
  4844.1 1254.37  4854.1 1255.29  4864.2 1254.43  4874.2 1254.31  4904.2 1255.13
  4917.8 1254.84  4966.9 1254.71  4987.8 1252.66  4994.6 1250.69  5000.1 1250.28
  5000.4 1249.78  5003.9 1249.78  5004.1 1250.28  5008.6 1250.68  5022.9 1253.40
  5030.9 1254.48  5037.3 1254.79  5105.6 1253.48  5125.6 1253.77  5155.6 1253.15
  5235.6 1253.13  5335.6 1252.40  5395.6 1252.55  5445.6 1253.26  5484.7 1253.12
#Mann=7,-1,0
  4439.1    0.05       0  4463.0    0.12       0  4578.8    0.05       0
  4663.2    0.12       0  4917.8    0.05       0  5000.1    0.05       0
  5004.1    0.05       0
Bank Sta=5000.1,5004.1
Exp/Cntr=0.3,0.1

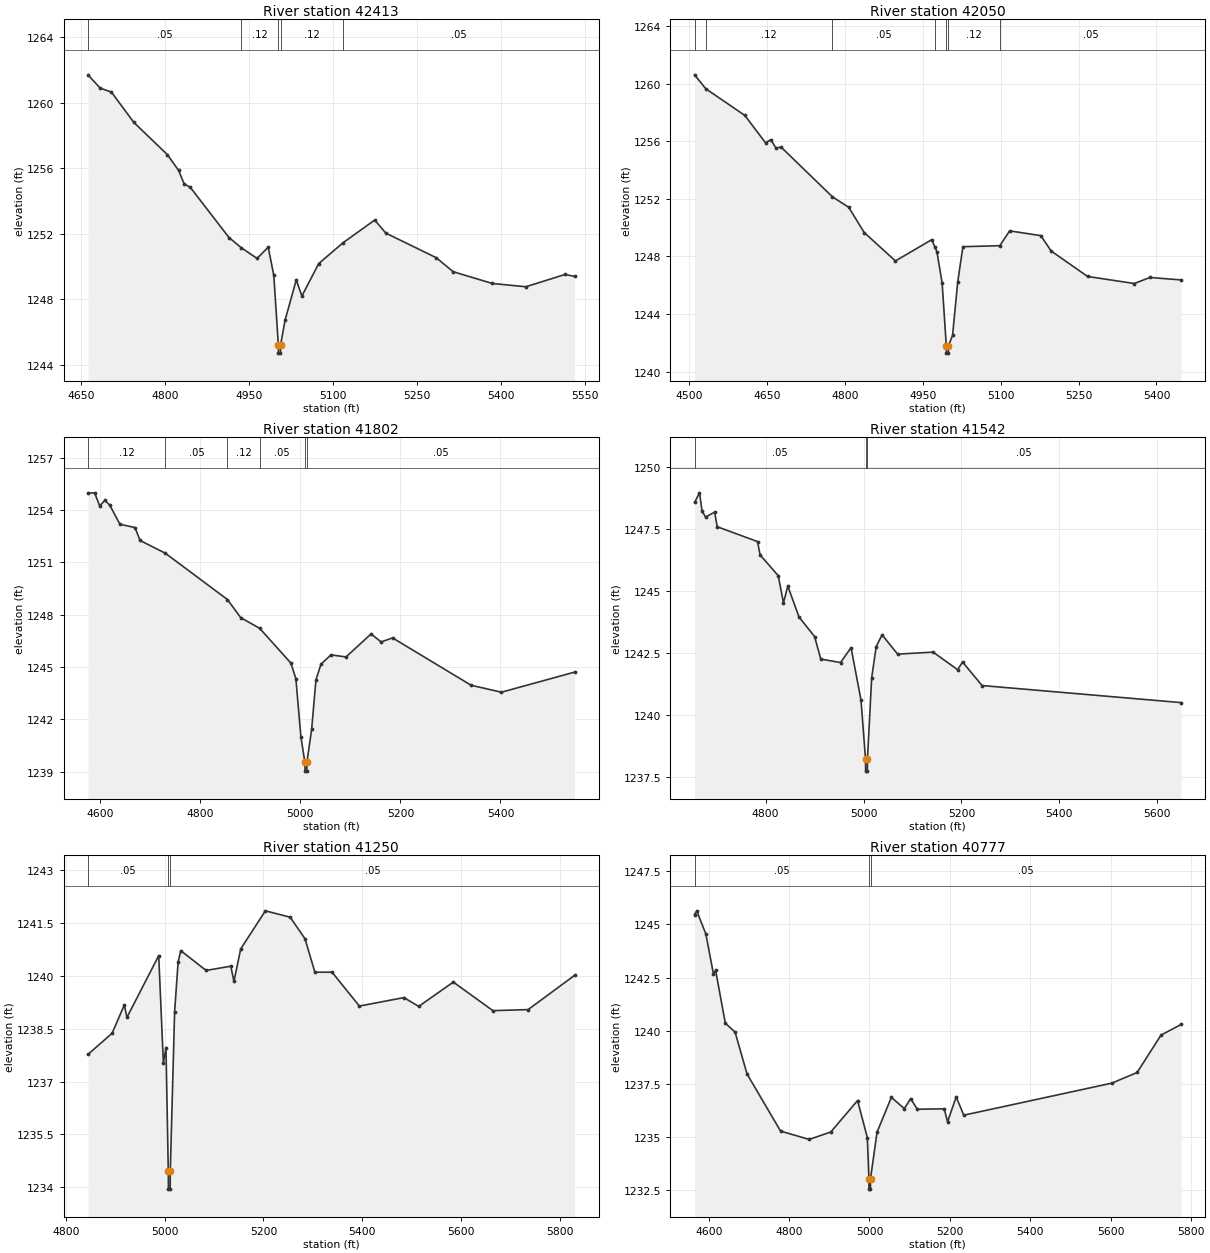
Type RM Length L Ch R = 1,42413,363,363,363
BEGIN DESCRIPTION:
Mapping XS 9f9ba7a5
END DESCRIPTION:
XS GIS Cut Line= 3
      2827223.96     10210984.59      2827725.67     10210966.36
      2828092.63     10210966.36
#Sta/Elev= 30
  4661.9 1261.70  4683.6 1260.89  4703.7 1260.65  4743.7 1258.80  4803.7 1256.83
  4823.7 1255.87  4833.7 1255.04  4844.5 1254.84  4913.8 1251.77  4935.7 1251.15
  4963.8 1250.50  4983.8 1251.18  4993.8 1249.46  5001.9 1245.22  5002.1 1244.72
  5005.6 1244.72  5005.9 1245.22  5013.9 1246.73  5033.9 1249.19  5043.9 1248.20
  5073.9 1250.18  5117.3 1251.45  5174.0 1252.84  5194.0 1252.04  5284.0 1250.54
  5314.0 1249.69  5384.0 1248.97  5444.0 1248.77  5514.0 1249.52  5530.9 1249.40
#Mann=5,-1,0
  4661.9    0.05       0  4935.7    0.12       0  5001.9    0.07       0
  5005.9    0.12       0  5117.3    0.05       0
Bank Sta=5001.9,5005.9
Exp/Cntr=0.3,0.1

Type RM Length L Ch R = 1,42050,248,248,248
BEGIN DESCRIPTION:
Mapping XS 05b76a36
END DESCRIPTION:
XS GIS Cut Line= 2
      2827188.88     10211226.77      2828125.80     10211208.55
#Sta/Elev= 30
  4510.3 1260.63  4532.0 1259.66  4607.1 1257.81  4647.1 1255.90  4657.1 1256.12
  4667.1 1255.54  4677.1 1255.60  4775.8 1252.15  4807.2 1251.42  4837.2 1249.66
  4897.2 1247.69  4967.2 1249.17  4973.5 1248.63  4977.2 1248.32  4987.2 1246.14
  4995.2 1241.78  4995.5 1241.28  4999.0 1241.28  4999.2 1241.78  5007.2 1242.51
  5017.2 1246.23  5027.2 1248.68  5098.3 1248.75  5117.2 1249.78  5177.2 1249.45
  5197.2 1248.38  5267.3 1246.61  5357.3 1246.12  5387.3 1246.54  5447.4 1246.37
#Mann=7,-1,0
  4510.3    0.05       0  4532.0    0.12       0  4775.8    0.05       0
  4973.5    0.12       0  4995.2    0.07       0  4999.2    0.12       0
  5098.3    0.05       0
Bank Sta=4995.2,4999.2
Exp/Cntr=0.3,0.1

Type RM Length L Ch R = 1,41802,260,260,260
BEGIN DESCRIPTION:
Mapping XS eec2f704
END DESCRIPTION:
XS GIS Cut Line= 3
      2827192.36     10211428.16      2827449.33     10211459.41
      2828161.53     10211415.72
#Sta/Elev= 30
  4575.6 1254.98  4589.0 1254.97  4599.1 1254.22  4609.2 1254.55  4619.2 1254.27
  4639.4 1253.18  4669.6 1252.99  4679.7 1252.25  4730.2 1251.52  4854.2 1248.87
  4880.9 1247.83  4918.7 1247.22  4981.1 1245.23  4991.1 1244.33  5001.1 1241.01
  5009.1 1239.54  5009.4 1239.04  5012.9 1239.04  5013.1 1239.54  5022.6 1241.43
  5031.2 1244.27  5041.2 1245.16  5061.2 1245.70  5091.3 1245.58  5141.4 1246.90
  5161.4 1246.44  5184.4 1246.67  5341.2 1243.96  5401.9 1243.56  5548.0 1244.71
#Mann=6,-1,0
  4575.6    0.12       0  4730.2    0.05       0  4854.2    0.12       0
  4918.7    0.05       0  5009.1    0.05       0  5013.1    0.05       0
Bank Sta=5009.1,5013.1
Exp/Cntr=0.3,0.1

Type RM Length L Ch R = 1,41542,292,292,292
BEGIN DESCRIPTION:
Mapping XS 2f71b088
END DESCRIPTION:
XS GIS Cut Line= 3
      2827284.37     10211583.64      2827718.38     10211736.41
      2828251.93     10211724.29
#Sta/Elev= 30
  4654.8 1248.58  4664.9 1248.97  4670.2 1248.23  4677.4 1247.99  4695.8 1248.19
  4701.1 1247.60  4783.4 1247.00  4788.7 1246.46  4825.8 1245.62  4836.4 1244.52
  4845.3 1245.20  4868.2 1243.95  4900.0 1243.16  4912.6 1242.25  4953.0 1242.11
  4974.5 1242.71  4994.8 1240.59  5004.0 1238.22  5004.3 1237.72  5007.8 1237.72
  5008.0 1238.22  5016.6 1241.49  5025.8 1242.75  5037.8 1243.23  5069.6 1242.45
  5142.2 1242.53  5192.2 1241.82  5202.2 1242.13  5242.2 1241.18  5648.6 1240.49
#Mann=3,-1,0
  4654.8    0.05       0  5004.0    0.05       0  5008.0    0.05       0
Bank Sta=5004,5008
Exp/Cntr=0.3,0.1

Type RM Length L Ch R = 1,41250,473,473,473
BEGIN DESCRIPTION:
Mapping XS e2ab347d
END DESCRIPTION:
XS GIS Cut Line= 3
      2827312.16     10211984.67      2827526.87     10211901.49
      2828280.74     10211863.16
#Sta/Elev= 30
  4844.9 1237.77  4893.8 1238.37  4918.4 1239.17  4923.8 1238.82  4988.1 1240.57
  4997.5 1237.53  5002.8 1237.96  5007.5 1234.45  5007.8 1233.95  5011.3 1233.95
  5011.5 1234.45  5020.3 1238.98  5027.4 1240.39  5032.8 1240.71  5084.0 1240.15
  5134.0 1240.27  5140.4 1239.84  5154.1 1240.76  5204.1 1241.84  5254.2 1241.66
  5284.2 1241.05  5304.3 1240.10  5339.0 1240.10  5394.4 1239.14  5484.5 1239.38
  5514.5 1239.13  5584.6 1239.82  5664.7 1239.01  5736.1 1239.04  5830.0 1240.01
#Mann=3,-1,0
  4844.9    0.05       0  5007.5    0.05       0  5011.5    0.05       0
Bank Sta=5007.5,5011.5
Exp/Cntr=0.3,0.1

Type RM Length L Ch R = 1,40777,410,410,410
BEGIN DESCRIPTION:
Mapping XS 87b49412
END DESCRIPTION:
XS GIS Cut Line= 2
      2827190.63     10212396.92      2828315.64     10211949.00
#Sta/Elev= 30
  4564.6 1245.46  4570.0 1245.64  4592.7 1244.55  4611.6 1242.67  4617.0 1242.84
  4641.2 1240.35  4665.5 1239.93  4695.2 1237.96  4778.8 1235.27  4849.9 1234.88
  4903.7 1235.23  4970.3 1236.71  4994.6 1234.97  4998.6 1233.04  4998.8 1232.54
  5002.3 1232.54  5002.6 1233.04  5018.8 1235.22  5054.4 1236.86  5086.7 1236.33
  5102.4 1236.80  5119.0 1236.30  5186.0 1236.32  5194.3 1235.71  5215.8 1236.88
  5234.6 1236.02  5603.3 1237.53  5666.1 1238.03  5725.5 1239.79  5775.5 1240.29
#Mann=3,-1,0
  4564.6    0.05       0  4998.6    0.03       0  5002.6    0.05       0
Bank Sta=4998.6,5002.6
Exp/Cntr=0.3,0.1

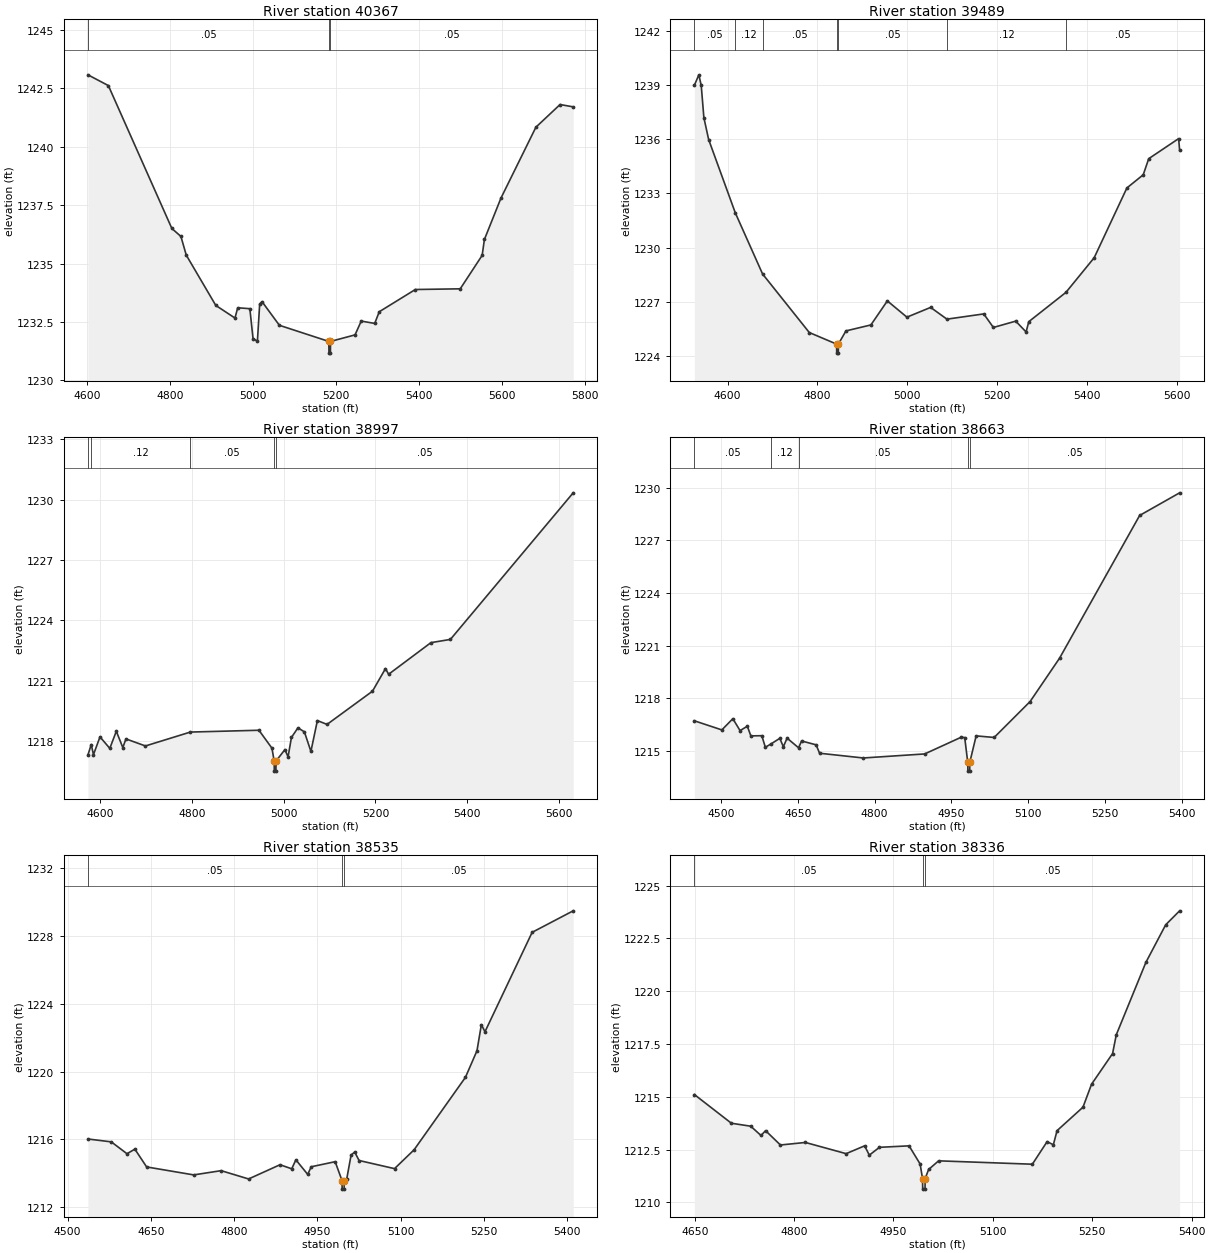
Type RM Length L Ch R = 1,40367,878,878,878
BEGIN DESCRIPTION:
Mapping XS 8da22d8f
END DESCRIPTION:
XS GIS Cut Line= 2
      2827369.49     10212698.99      2828445.83     10212244.15
#Sta/Elev= 30
  4602.8 1243.07  4652.0 1242.61  4804.9 1236.50  4826.7 1236.16  4839.6 1235.36
  4910.7 1233.21  4956.9 1232.67  4963.5 1233.11  4992.7 1233.07  5000.4 1231.79
  5010.9 1231.68  5016.4 1233.27  5022.1 1233.37  5063.8 1232.36  5182.9 1231.67
  5183.2 1231.17  5186.7 1231.17  5186.9 1231.67  5246.0 1231.95  5260.9 1232.54
  5293.4 1232.44  5304.3 1232.94  5391.2 1233.89  5499.3 1233.92  5552.1 1235.35
  5557.5 1236.03  5597.4 1237.80  5681.5 1240.83  5739.7 1241.80  5771.3 1241.70
#Mann=3,-1,0
  4602.8    0.05       0  5182.9    0.05       0  5186.9    0.05       0
Bank Sta=5182.9,5186.9
Exp/Cntr=0.3,0.1

Type RM Length L Ch R = 1,39489,492,492,492
BEGIN DESCRIPTION:
BYRNES CREEK 71.0
END DESCRIPTION:
XS GIS Cut Line= 3
      2827605.71     10213403.10      2828051.75     10213243.00
      2828563.74     10212917.68
#Sta/Elev= 30
  4526.1 1238.98  4536.1 1239.56  4541.4 1238.97  4547.3 1237.19  4557.9 1235.98
  4617.3 1231.92  4678.0 1228.54  4782.0 1225.30  4842.8 1224.66  4843.1 1224.16
  4846.6 1224.16  4846.8 1224.66  4863.6 1225.39  4919.2 1225.72  4955.8 1227.05
  4999.4 1226.15  5052.2 1226.69  5088.5 1226.04  5170.5 1226.33  5191.9 1225.58
  5241.6 1225.93  5264.8 1225.33  5270.7 1225.90  5353.4 1227.52  5416.4 1229.44
  5489.2 1233.30  5525.6 1234.03  5537.8 1234.92  5604.4 1236.03  5606.6 1235.39
#Mann=7,-1,0
  4526.1    0.05       0  4617.3    0.12       0  4678.0    0.05       0
  4842.8    0.05       0  4846.8    0.05       0  5088.5    0.12       0
  5353.4    0.05       0
Bank Sta=4842.8,4846.8
Exp/Cntr=0.3,0.1

Type RM Length L Ch R = 1,38997,334,334,334
BEGIN DESCRIPTION:
Mapping XS 7b8d9e2a
END DESCRIPTION:
XS GIS Cut Line= 2
      2827904.96     10214009.69      2828631.29     10213239.99
#Sta/Elev= 30
  4572.9 1217.32  4580.1 1217.84  4585.0 1217.34  4599.2 1218.22  4620.6 1217.65
  4634.8 1218.50  4649.0 1217.69  4655.8 1218.12  4698.3 1217.77  4796.4 1218.46
  4945.9 1218.55  4974.2 1217.66  4979.1 1217.02  4979.4 1216.52  4982.9 1216.52
  4983.1 1217.02  5002.5 1217.59  5009.4 1217.23  5016.7 1218.19  5030.9 1218.67
  5045.0 1218.47  5059.2 1217.50  5073.3 1219.03  5094.4 1218.84  5193.5 1220.49
  5221.8 1221.61  5228.7 1221.33  5320.9 1222.90  5363.4 1223.06  5631.2 1230.34
#Mann=5,-1,0
  4572.9    0.05       0  4580.1    0.12       0  4796.4    0.05       0
  4979.1    0.03       0  4983.1    0.05       0
Bank Sta=4979.1,4983.1
Exp/Cntr=0.3,0.1

Type RM Length L Ch R = 1,38663,128,128,128
BEGIN DESCRIPTION:
Mapping XS ebd20b06
END DESCRIPTION:
XS GIS Cut Line= 3
      2827976.54     10214350.03      2828192.11     10214119.37
      2828682.21     10213719.56
#Sta/Elev= 30
  4448.0 1216.71  4501.7 1216.19  4523.2 1216.83  4537.3 1216.15  4551.5 1216.40
  4558.4 1215.85  4579.8 1215.86  4586.7 1215.20  4597.1 1215.38  4615.0 1215.71
  4621.9 1215.23  4629.2 1215.72  4651.7 1215.17  4657.5 1215.56  4685.9 1215.34
  4692.7 1214.86  4778.1 1214.59  4898.0 1214.82  4969.9 1215.78  4976.3 1215.75
  4982.2 1214.34  4982.5 1213.84  4986.0 1213.84  4986.2 1214.34  4998.6 1215.85
  5033.8 1215.76  5104.1 1217.81  5161.6 1220.28  5318.1 1228.42  5396.2 1229.71
#Mann=5,-1,0
  4448.0    0.05       0  4597.1    0.12       0  4651.7    0.05       0
  4982.2    0.05       0  4986.2    0.05       0
Bank Sta=4982.2,4986.2
Exp/Cntr=0.3,0.1

Type RM Length L Ch R = 1,38535,199,199,199
BEGIN DESCRIPTION:
Mapping XS 1116d0ab
END DESCRIPTION:
XS GIS Cut Line= 3
      2828049.84     10214416.86      2828306.37     10214160.34
      2828703.07     10213836.94
#Sta/Elev= 30
  4536.6 1216.03  4578.7 1215.86  4607.0 1215.16  4621.2 1215.43  4642.4 1214.38
  4727.2 1213.91  4776.7 1214.16  4826.2 1213.67  4882.8 1214.51  4903.9 1214.27
  4911.4 1214.80  4932.7 1213.94  4939.1 1214.39  4982.2 1214.69  4994.6 1213.57
  4994.8 1213.07  4998.3 1213.07  4998.6 1213.57  5003.0 1213.66  5010.9 1215.08
  5017.4 1215.26  5025.3 1214.76  5089.2 1214.28  5124.4 1215.39  5217.0 1219.67
  5237.8 1221.24  5245.7 1222.78  5252.2 1222.36  5337.2 1228.23  5411.2 1229.50
#Mann=3,-1,0
  4536.6    0.05       0  4994.6    0.05       0  4998.6    0.05       0
Bank Sta=4994.6,4998.6
Exp/Cntr=0.3,0.1

Type RM Length L Ch R = 1,38336,290,290,290
BEGIN DESCRIPTION:
Mapping XS e47c0601
END DESCRIPTION:
XS GIS Cut Line= 2
      2828119.56     10214442.56      2828774.47     10214114.46
#Sta/Elev= 30
  4649.4 1215.11  4705.3 1213.75  4734.5 1213.61  4750.0 1213.17  4756.9 1213.40
  4779.3 1212.72  4817.0 1212.84  4878.5 1212.31  4906.4 1212.68  4913.5 1212.24
  4928.8 1212.61  4973.5 1212.68  4990.2 1211.82  4993.8 1211.13  4994.1 1210.63
  4997.6 1210.63  4997.8 1211.13  5003.0 1211.56  5018.1 1211.97  5159.6 1211.81
  5181.9 1212.88  5191.3 1212.73  5196.9 1213.40  5236.0 1214.51  5249.0 1215.60
  5280.7 1217.05  5286.3 1217.94  5331.0 1221.37  5360.9 1223.15  5381.9 1223.81
#Mann=3,-1,0
  4649.4    0.05       0  4993.8    0.03       0  4997.8    0.05       0
Bank Sta=4993.8,4997.8
Exp/Cntr=0.3,0.1

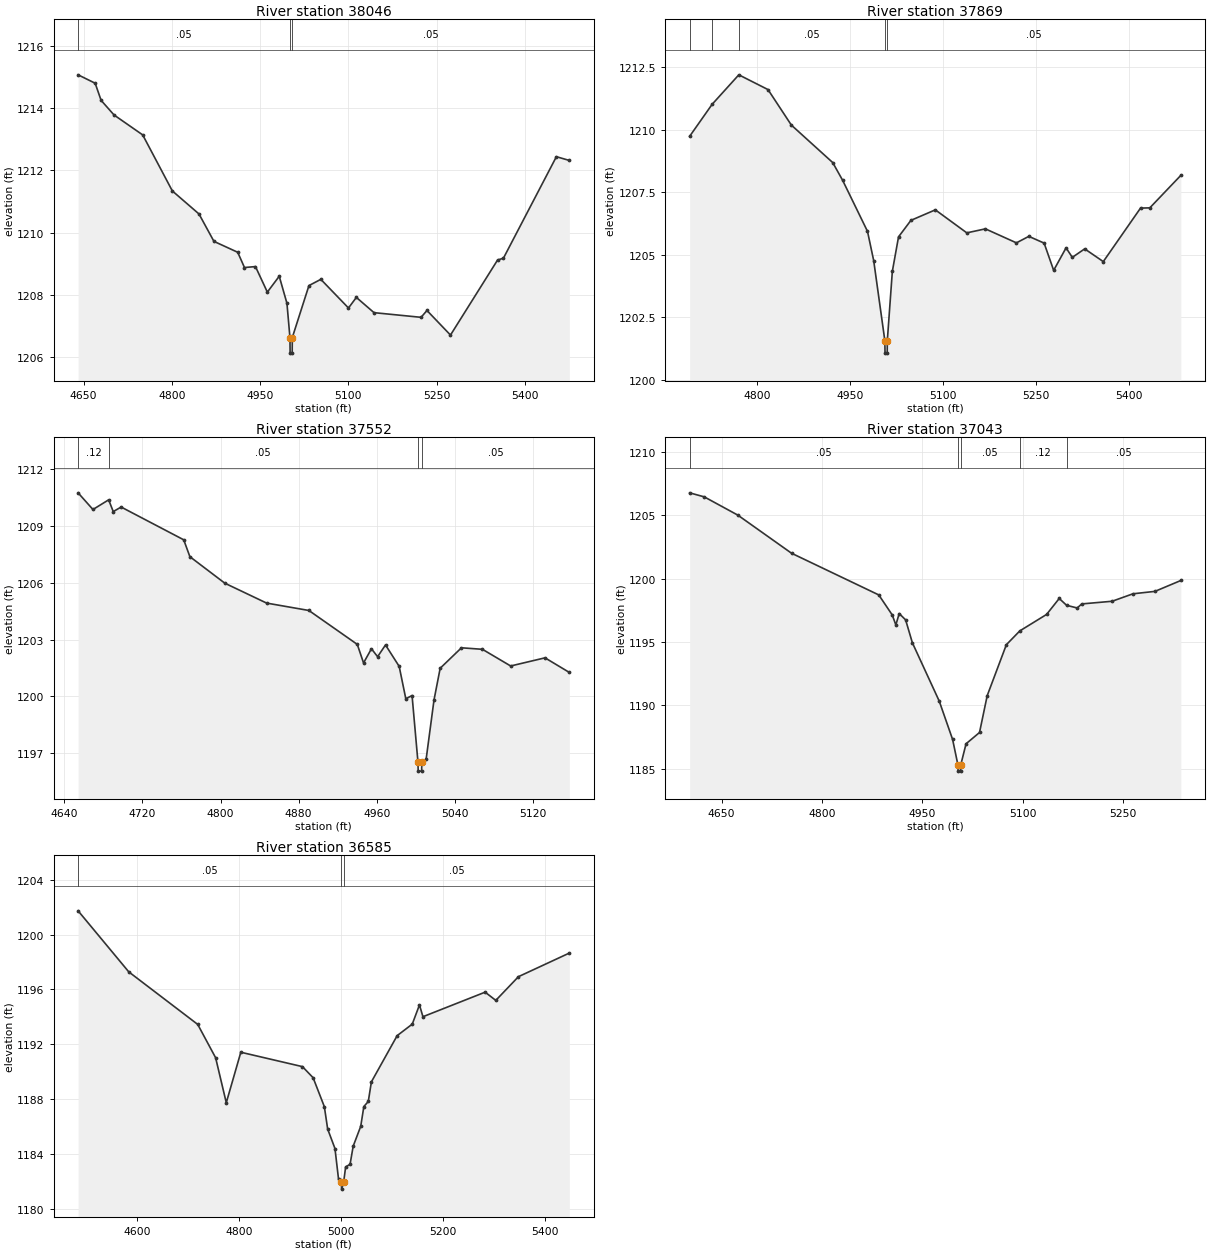
Type RM Length L Ch R = 1,38046,177,177,177
BEGIN DESCRIPTION:
Mapping XS 88aecae9
END DESCRIPTION:
XS GIS Cut Line= 3
      2828116.92     10214510.28      2828573.96     10214572.78
      2828947.67     10214572.78
#Sta/Elev= 30
  4640.6 1215.07  4669.6 1214.80  4679.7 1214.25  4701.7 1213.78  4750.4 1213.14
  4800.8 1211.34  4846.1 1210.60  4871.5 1209.72  4911.9 1209.37  4923.4 1208.88
  4942.1 1208.91  4962.3 1208.09  4982.5 1208.60  4995.6 1207.73  5000.7 1206.63
  5001.0 1206.13  5004.5 1206.13  5004.7 1206.63  5033.0 1208.30  5053.2 1208.50
  5100.2 1207.58  5113.6 1207.92  5143.6 1207.43  5223.6 1207.28  5233.6 1207.50
  5273.6 1206.71  5353.6 1209.12  5363.6 1209.18  5453.6 1212.44  5475.6 1212.32
#Mann=3,-1,0
  4640.6    0.05       0  5000.7    0.05       0  5004.7    0.05       0
Bank Sta=5000.7,5004.7
Exp/Cntr=0.3,0.1

Type RM Length L Ch R = 1,37869,317,317,317
BEGIN DESCRIPTION:
Mapping XS 4d338741
END DESCRIPTION:
XS GIS Cut Line= 3
      2828100.30     10214736.68      2828265.41     10214714.40
      2828890.63     10214751.05
#Sta/Elev= 30
  4691.3 1209.73  4727.6 1211.01  4770.7 1212.19  4817.8 1211.60  4855.5 1210.18
  4922.3 1208.68  4938.3 1207.97  4978.4 1205.93  4988.4 1204.76  5006.4 1201.56
  5006.7 1201.06  5010.2 1201.06  5010.4 1201.56  5018.5 1204.33  5028.5 1205.71
  5048.5 1206.37  5087.9 1206.79  5138.7 1205.87  5168.7 1206.03  5218.8 1205.47
  5238.8 1205.73  5263.5 1205.46  5278.9 1204.37  5298.9 1205.27  5309.0 1204.89
  5329.0 1205.23  5359.0 1204.72  5419.1 1206.86  5434.1 1206.87  5484.2 1208.17
#Mann=5,-1,0
  4691.3    0.05       0  4727.6    0.12       0  4770.7    0.05       0
  5006.4    0.03       0  5010.4    0.05       0
Bank Sta=5006.4,5010.4
Exp/Cntr=0.3,0.1

Type RM Length L Ch R = 1,37552,509,509,509
BEGIN DESCRIPTION:
Mapping XS 8d2c403b
END DESCRIPTION:
XS GIS Cut Line= 2
      2828157.92     10214799.33      2828552.24     10215111.93
#Sta/Elev= 30
  4654.1 1210.75  4669.3 1209.87  4685.4 1210.38  4690.1 1209.76  4698.2 1210.00
  4762.3 1208.27  4768.6 1207.38  4804.4 1205.98  4847.2 1204.93  4890.5 1204.54
  4940.1 1202.75  4946.5 1201.77  4954.6 1202.52  4960.9 1202.10  4969.0 1202.72
  4983.0 1201.59  4989.8 1199.88  4996.2 1200.05  5002.2 1196.56  5002.5 1196.06
  5006.0 1196.06  5006.2 1196.56  5010.6 1196.68  5018.7 1199.82  5025.0 1201.49
  5046.8 1202.57  5068.3 1202.49  5097.2 1201.61  5132.4 1202.04  5157.3 1201.27
#Mann=4,-1,0
  4654.1    0.12       0  4685.4    0.05       0  5002.2    0.05       0
  5006.2    0.05       0
Bank Sta=5002.2,5006.2
Exp/Cntr=0.3,0.1

Type RM Length L Ch R = 1,37043,458,458,458
BEGIN DESCRIPTION:
Mapping XS 3a6f05cb
END DESCRIPTION:
XS GIS Cut Line= 3
      2827653.86     10215254.86      2828208.33     10215296.78
      2828371.12     10215225.15
#Sta/Elev= 30
  4602.3 1206.78  4624.2 1206.46  4674.3 1205.02  4754.6 1202.01  4884.9 1198.72
  4905.0 1197.14  4910.4 1196.35  4915.4 1197.25  4925.0 1196.75  4935.1 1194.94
  4975.2 1190.34  4995.2 1187.31  5003.1 1185.31  5003.4 1184.81  5007.1 1184.81
  5007.4 1185.31  5015.3 1186.97  5035.4 1187.86  5046.9 1190.77  5075.5 1194.79
  5095.6 1195.88  5135.6 1197.18  5154.5 1198.44  5165.5 1197.90  5181.3 1197.69
  5188.2 1198.01  5233.5 1198.22  5264.7 1198.81  5297.5 1199.00  5336.2 1199.86
#Mann=5,-1,0
  4602.3    0.05       0  5003.1    0.05       0  5007.4    0.05       0
  5095.6    0.12       0  5165.5    0.05       0
Bank Sta=5003.1,5007.4
Exp/Cntr=0.3,0.1

Type RM Length L Ch R = 1,36585,498,498,498
BEGIN DESCRIPTION:
BYRNES CREEK 65.0
END DESCRIPTION:
XS GIS Cut Line= 3
      2827805.71     10216003.09      2828197.50     10215669.00
      2828455.68     10215303.12
#Sta/Elev= 30
  4485.1 1201.73  4584.4 1197.28  4719.5 1193.45  4754.6 1191.02  4775.5 1187.74
  4804.0 1191.42  4924.8 1190.37  4945.7 1189.56  4967.7 1187.45  4974.2 1185.82
  4988.5 1184.40  4995.5 1182.17  5001.2 1181.94  5001.5 1181.44  5005.5 1181.94
  5009.4 1183.06  5018.1 1183.25  5024.2 1184.57  5039.0 1186.02  5045.1 1187.46
  5053.8 1187.83  5059.9 1189.26  5110.4 1192.63  5140.0 1193.47  5154.1 1194.87
  5160.9 1194.01  5282.8 1195.80  5303.7 1195.20  5348.1 1196.93  5447.8 1198.65
#Mann=3,-1,0
  4485.1    0.05       0  5001.2    0.05       0  5005.5    0.05       0
Bank Sta=5001.2,5005.5
Exp/Cntr=0.3,0.1