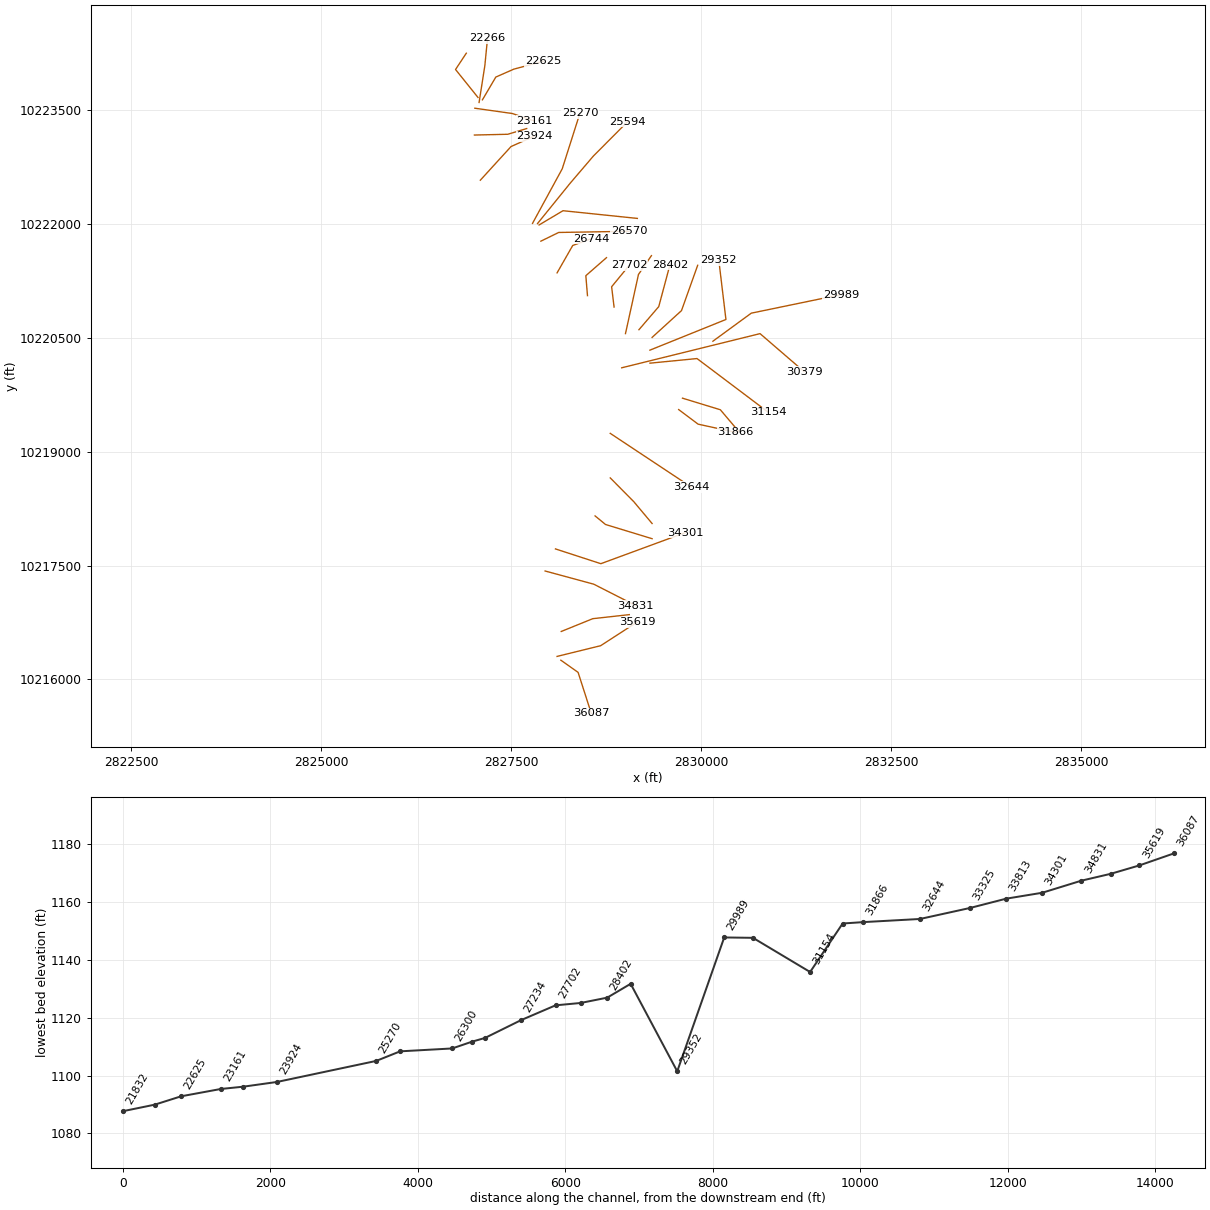
HEC-RAS study BYRNES CREEK.prj: BYRNES CREEK Base Level Engineering

--- BYRNES CREEK.g01 (geometry) --- (continued)

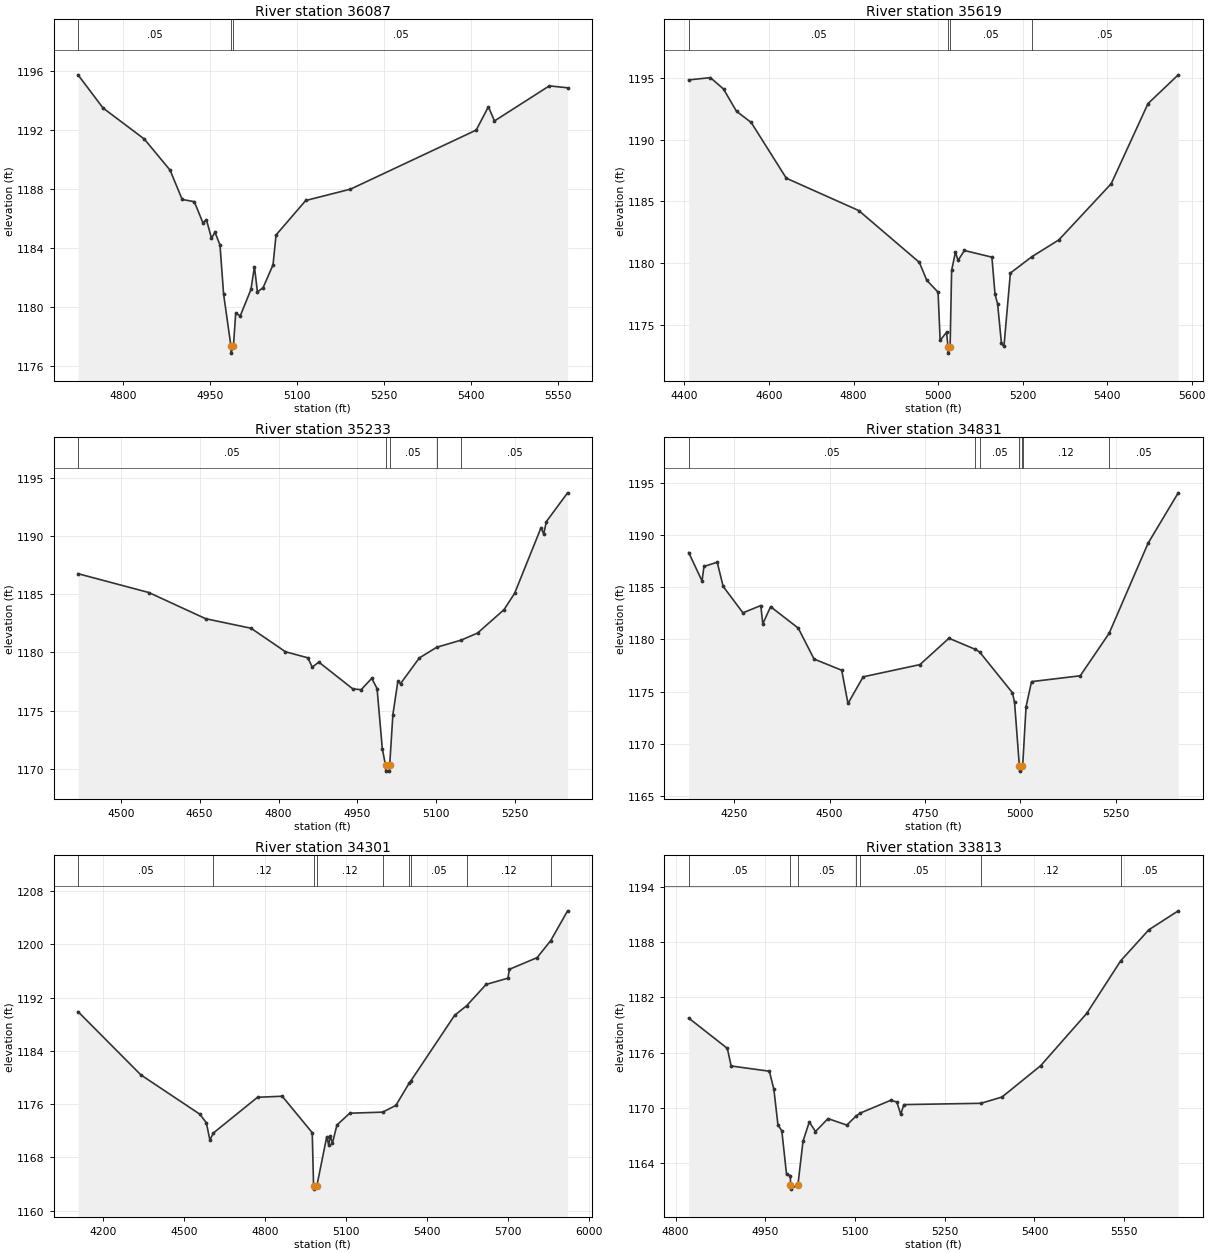
Type RM Length L Ch R = 1,36087,468,468,468
BEGIN DESCRIPTION:
BYRNES CREEK 64.0
END DESCRIPTION:
XS GIS Cut Line= 3
      2828155.71     10216253.09      2828382.25     10216093.00
      2828555.70     10215553.08
#Sta/Elev= 30
  4722.6 1195.73  4765.7 1193.48  4837.0 1191.37  4881.4 1189.26  4902.3 1187.27
  4923.2 1187.12  4938.0 1185.69  4944.1 1185.90  4952.8 1184.64  4958.9 1185.04
  4967.5 1184.18  4973.7 1180.86  4986.3 1177.34  4986.6 1176.84  4990.7 1177.34
  4994.6 1179.53  5002.6 1179.38  5020.9 1181.16  5026.9 1182.71  5032.1 1180.99
  5041.9 1181.29  5059.0 1182.83  5064.2 1184.86  5115.4 1187.20  5192.6 1187.97
  5409.5 1191.98  5430.5 1193.56  5441.0 1192.60  5535.6 1194.98  5567.1 1194.85
#Mann=3,-1,0
  4722.6    0.05       0  4986.3    0.05       0  4990.7    0.05       0
Bank Sta=4986.3,4990.7
Exp/Cntr=0.3,0.1

Type RM Length L Ch R = 1,35619,386,386,386
BEGIN DESCRIPTION:
BYRNES CREEK 63.0
END DESCRIPTION:
XS GIS Cut Line= 3
      2828105.71     10216303.12      2828678.75     10216444.00
      2829155.65     10216753.09
#Sta/Elev= 30
  4409.9 1194.84  4461.4 1195.02  4492.3 1194.10  4523.1 1192.29  4557.8 1191.39
  4640.9 1186.87  4812.2 1184.25  4955.7 1180.05  4973.2 1178.60  5000.0 1177.63
  5004.9 1173.72  5020.1 1174.38  5023.5 1173.19  5023.9 1172.69  5028.5 1173.19
  5032.1 1179.40  5041.2 1180.89  5047.2 1180.20  5062.3 1181.01  5127.4 1180.47
  5134.8 1177.45  5140.8 1176.70  5150.0 1173.48  5155.9 1173.23  5171.1 1179.18
  5222.1 1180.51  5285.8 1181.87  5409.8 1186.43  5496.8 1192.92  5568.3 1195.25
#Mann=4,-1,0
  4409.9    0.05       0  5023.5    0.05       0  5028.5    0.05       0
  5222.1    0.05       0
Bank Sta=5023.5,5028.5
Exp/Cntr=0.3,0.1

Type RM Length L Ch R = 1,35233,402,402,402
BEGIN DESCRIPTION:
BYRNES CREEK 62.0
END DESCRIPTION:
XS GIS Cut Line= 3
      2828160.83     10216631.61      2828575.72     10216800.00
      2829055.73     10216853.12
#Sta/Elev= 30
  4418.8 1186.77  4553.5 1185.15  4661.5 1182.90  4747.8 1182.08  4813.2 1180.06
  4855.7 1179.54  4864.1 1178.74  4876.6 1179.17  4941.2 1176.87  4957.1 1176.80
  4977.2 1177.78  4987.3 1176.90  4997.3 1171.73  5003.4 1170.30  5003.9 1169.80
  5010.8 1169.80  5011.3 1170.30  5017.4 1174.66  5026.9 1177.53  5031.9 1177.32
  5067.7 1179.53  5100.9 1180.45  5147.3 1181.06  5178.4 1181.67  5228.7 1183.68
  5248.8 1185.08  5299.1 1190.73  5304.1 1190.18  5309.2 1191.25  5349.5 1193.72
#Mann=5,-1,0
  4418.8    0.05       0  5003.4    0.05       0  5011.3    0.05       0
  5100.9    0.12       0  5147.3    0.05       0
Bank Sta=5003.4,5011.3
Exp/Cntr=0.3,0.1

Type RM Length L Ch R = 1,34831,530,530,530
BEGIN DESCRIPTION:
Mapping XS fbbb909f
END DESCRIPTION:
XS GIS Cut Line= 3
      2827948.39     10217427.65      2828588.56     10217254.05
      2829141.28     10216972.26
#Sta/Elev= 30
  4130.4 1188.31  4165.4 1185.59  4170.5 1186.98  4205.2 1187.38  4220.8 1185.07
  4272.7 1182.54  4319.5 1183.24  4324.7 1181.49  4345.2 1183.13  4417.7 1181.08
  4459.2 1178.12  4531.7 1177.05  4548.1 1173.87  4587.9 1176.42  4736.8 1177.59
  4812.9 1180.11  4881.2 1179.06  4893.0 1178.81  4979.3 1174.90  4984.9 1173.97
  4997.5 1167.90  4998.0 1167.40  5005.5 1167.90  5006.3 1167.96  5015.0 1173.55
  5029.4 1175.96  5157.1 1176.52  5233.0 1180.59  5335.0 1189.20  5414.1 1194.02
#Mann=7,-1,0
  4130.4    0.05       0  4881.2    0.12       0  4893.0    0.05       0
  4997.5    0.05       0  5005.5    0.05       0  5006.3    0.12       0
  5233.0    0.05       0
Bank Sta=4997.5,5005.5
Exp/Cntr=0.3,0.1

Type RM Length L Ch R = 1,34301,488,488,488
BEGIN DESCRIPTION:
BYRNES CREEK 60.0
END DESCRIPTION:
XS GIS Cut Line= 3
      2828084.41     10217718.40      2828681.62     10217523.96
      2829791.74     10217932.88
#Sta/Elev= 30
  4108.2 1189.90  4340.9 1180.39  4558.9 1174.49  4582.8 1173.21  4596.1 1170.61
  4608.8 1171.66  4772.2 1177.03  4863.6 1177.19  4974.7 1171.71  4979.6 1163.73
  4980.1 1163.23  4991.8 1163.73  5028.3 1171.10  5035.6 1169.86  5041.0 1171.17
  5049.6 1170.18  5066.1 1172.87  5113.6 1174.64  5235.1 1174.80  5284.1 1175.81
  5333.2 1179.15  5338.7 1179.45  5501.5 1189.35  5545.9 1190.79  5618.0 1193.99
  5698.7 1194.93  5704.0 1196.26  5806.3 1198.01  5856.6 1200.55  5919.3 1205.05
#Mann=9,-1,0
  4108.2    0.05       0  4608.8    0.12       0  4979.6    0.07       0
  4991.8    0.12       0  5235.1    0.05       0  5333.2    0.12       0
  5338.7    0.05       0  5545.9    0.12       0  5856.6    0.05       0
Bank Sta=4979.6,4991.8
Exp/Cntr=0.3,0.1

Type RM Length L Ch R = 1,33813,488,488,488
BEGIN DESCRIPTION:
BYRNES CREEK 59.0
END DESCRIPTION:
XS GIS Cut Line= 3
      2828605.68     10218153.11      2828743.25     10218040.00
      2829355.67     10217853.12
#Sta/Elev= 30
  4821.9 1179.75  4886.5 1176.46  4892.9 1174.55  4956.8 1173.98  4964.3 1172.02
  4971.1 1168.17  4977.6 1167.51  4985.5 1162.79  4992.0 1162.66  4992.1 1161.69
  4992.6 1161.19  5004.6 1161.69  5013.0 1166.38  5023.5 1168.48  5033.9 1167.44
  5054.8 1168.84  5086.2 1168.14  5101.7 1169.12  5109.1 1169.45  5159.4 1170.82
  5169.8 1170.65  5176.4 1169.31  5181.6 1170.36  5310.3 1170.50  5345.7 1171.18
  5410.3 1174.58  5487.4 1180.26  5544.1 1185.96  5591.1 1189.32  5640.3 1191.38
#Mann=7,-1,0
  4821.9    0.05       0  4992.1    0.05       0  5004.6    0.05       0
  5101.7    0.12       0  5109.1    0.05       0  5310.3    0.12       0
  5544.1    0.05       0
Bank Sta=4992.1,5004.6
Exp/Cntr=0.3,0.1

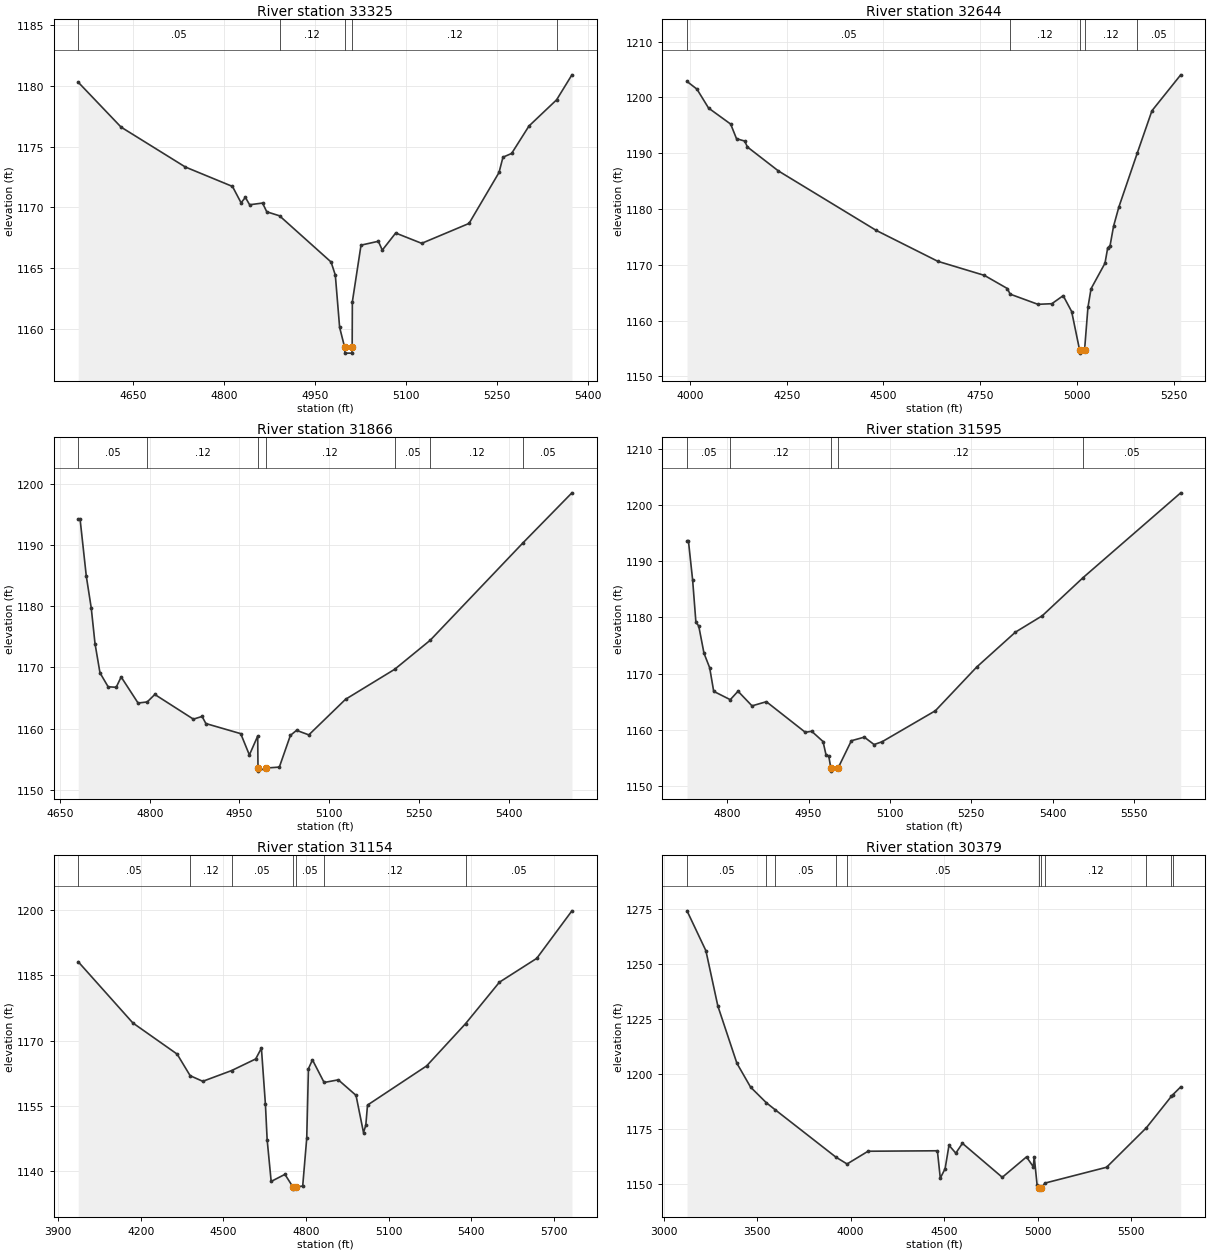
Type RM Length L Ch R = 1,33325,681,681,681
BEGIN DESCRIPTION:
BYRNES CREEK 58.0
END DESCRIPTION:
XS GIS Cut Line= 3
      2828805.69     10218653.11      2829115.25     10218340.00
      2829355.67     10218053.12
#Sta/Elev= 30
  4559.7 1180.32  4630.4 1176.62  4736.5 1173.33  4814.2 1171.73  4828.4 1170.38
  4835.5 1170.83  4842.5 1170.22  4863.8 1170.36  4870.8 1169.64  4891.8 1169.31
  4976.9 1165.50  4983.9 1164.42  4991.0 1160.11  4999.2 1158.49  4999.7 1157.99
  5011.2 1157.99  5011.7 1158.49  5012.0 1162.22  5026.3 1166.89  5054.9 1167.21
  5061.4 1166.48  5083.5 1167.89  5126.4 1167.04  5204.5 1168.68  5254.0 1172.88
  5260.5 1174.14  5274.8 1174.45  5303.4 1176.71  5349.0 1178.87  5374.3 1180.93
#Mann=5,-1,0
  4559.7    0.05       0  4891.8    0.12       0  4999.2    0.07       0
  5011.7    0.12       0  5349.0    0.05       0
Bank Sta=4999.2,5011.7
Exp/Cntr=0.3,0.1

Type RM Length L Ch R = 1,32644,778,778,778
BEGIN DESCRIPTION:
Mapping XS 1f4d50e2
END DESCRIPTION:
XS GIS Cut Line= 2
      2828805.53     10219239.75      2829868.90     10218534.45
#Sta/Elev= 30
  3992.2 1202.87  4017.8 1201.50  4047.9 1198.10  4105.0 1195.23  4120.1 1192.61
  4141.1 1192.19  4148.4 1191.12  4228.4 1186.83  4481.0 1176.18  4640.4 1170.63
  4760.7 1168.11  4820.4 1165.74  4827.1 1164.75  4899.1 1162.92  4935.1 1163.03
  4964.4 1164.47  4986.3 1161.63  5007.0 1154.67  5007.5 1154.17  5019.6 1154.67
  5028.4 1162.38  5036.4 1165.71  5072.4 1170.28  5079.5 1173.05  5085.5 1173.41
  5094.6 1176.92  5108.3 1180.36  5155.9 1190.04  5193.8 1197.62  5268.2 1204.06
#Mann=5,-1,0
  3992.2    0.05       0  4827.1    0.12       0  5007.0    0.07       0
  5019.6    0.12       0  5155.9    0.05       0
Bank Sta=5007,5019.6
Exp/Cntr=0.3,0.1

Type RM Length L Ch R = 1,31866,271,271,271
BEGIN DESCRIPTION:
BYRNES CREEK 55.0
END DESCRIPTION:
XS GIS Cut Line= 3
      2829705.70     10219553.10      2829961.25     10219361.00
      2830455.72     10219253.10
#Sta/Elev= 30
  4680.3 1194.23  4683.4 1194.23  4693.8 1184.91  4702.1 1179.70  4708.4 1173.88
  4716.7 1169.12  4730.3 1166.85  4743.8 1166.76  4752.1 1168.45  4780.4 1164.19
  4795.7 1164.37  4808.4 1165.59  4872.9 1161.56  4887.5 1162.00  4893.8 1160.84
  4952.1 1159.19  4966.6 1155.71  4980.5 1158.80  4981.0 1153.57  4981.5 1153.07
  4993.9 1153.57  5016.7 1153.73  5035.2 1158.91  5045.5 1159.73  5066.0 1158.99
  5127.4 1164.80  5209.6 1169.70  5269.0 1174.44  5424.4 1190.37  5506.1 1198.52
#Mann=7,-1,0
  4680.3    0.05       0  4795.7    0.12       0  4981.0    0.07       0
  4993.9    0.12       0  5209.6    0.05       0  5269.0    0.12       0
  5424.4    0.05       0
Bank Sta=4981,4993.9
Exp/Cntr=0.3,0.1

Type RM Length L Ch R = 1,31595,441,441,441
BEGIN DESCRIPTION:
BYRNES CREEK 54.0
END DESCRIPTION:
XS GIS Cut Line= 3
      2829755.71     10219703.10      2830253.75     10219550.79
      2830505.69     10219253.11
#Sta/Elev= 30
  4725.7 1193.67  4728.3 1193.67  4736.1 1186.63  4742.1 1179.14  4747.3 1178.49
  4757.0 1173.63  4767.5 1171.03  4774.9 1166.83  4805.5 1165.34  4819.8 1166.85
  4845.6 1164.24  4872.1 1164.98  4944.0 1159.52  4955.7 1159.71  4976.6 1157.88
  4982.0 1155.56  4987.2 1155.28  4991.1 1153.10  4991.6 1152.60  5004.1 1153.10
  5028.9 1158.02  5052.8 1158.66  5070.8 1157.34  5085.6 1157.84  5183.9 1163.37
  5260.2 1171.17  5331.6 1177.39  5381.1 1180.31  5456.5 1187.12  5636.5 1202.23
#Mann=5,-1,0
  4725.7    0.05       0  4805.5    0.12       0  4991.1    0.07       0
  5004.1    0.12       0  5456.5    0.05       0
Bank Sta=4991.1,5004.1
Exp/Cntr=0.3,0.1

Type RM Length L Ch R = 1,31154,775,775,775
BEGIN DESCRIPTION:
Mapping XS 6ea41417
END DESCRIPTION:
XS GIS Cut Line= 3
      2829328.36     10220164.15      2829946.82     10220224.91
      2830881.44     10219520.15
#Sta/Elev= 30
  3973.0 1188.15  4171.3 1174.07  4332.0 1166.90  4379.3 1161.93  4425.1 1160.64
  4529.7 1163.11  4617.1 1165.78  4637.9 1168.27  4652.5 1155.31  4658.7 1147.22
  4673.3 1137.60  4723.3 1139.23  4752.2 1136.33  4752.7 1135.83  4765.2 1136.33
  4787.8 1136.55  4802.4 1147.55  4808.6 1163.55  4823.2 1165.57  4865.5 1160.37
  4916.9 1160.98  4981.3 1157.41  5008.5 1148.83  5016.8 1150.54  5023.0 1155.17
  5237.5 1164.18  5378.8 1173.90  5501.8 1183.45  5637.2 1188.93  5765.0 1199.87
#Mann=7,-1,0
  3973.0    0.05       0  4379.3    0.12       0  4529.7    0.05       0
  4752.2    0.07       0  4765.2    0.05       0  4865.5    0.12       0
  5378.8    0.05       0
Bank Sta=4752.2,4765.2
Exp/Cntr=0.3,0.1

Type RM Length L Ch R = 1,30379,390,390,390
BEGIN DESCRIPTION:
BYRNES CREEK 53.0
END DESCRIPTION:
XS GIS Cut Line= 3
      2828955.71     10220103.12      2830776.25     10220553.00
      2831355.71     10220053.09
#Sta/Elev= 30
  3124.7 1274.34  3225.7 1256.17  3289.5 1231.04  3391.5 1204.94  3464.6 1194.09
  3549.6 1186.92  3597.3 1183.71  3921.1 1162.21  3980.8 1159.10  4092.9 1164.90
  4463.8 1165.11  4479.3 1152.65  4505.0 1156.93  4525.9 1167.62  4562.2 1164.02
  4597.7 1168.50  4810.9 1153.03  4940.4 1162.32  4976.6 1157.85  4981.8 1162.33
  4997.1 1149.53  5006.7 1148.15  5007.2 1147.65  5019.8 1148.15  5038.9 1150.39
  5368.7 1157.61  5581.3 1175.56  5715.3 1189.89  5722.6 1190.60  5765.3 1194.19
#Mann=11,-1,0
  3124.7    0.05       0  3549.6    0.12       0  3597.3    0.05       0
  3921.1    0.12       0  3980.8    0.05       0  5006.7    0.05       0
  5019.8    0.05       0  5038.9    0.12       0  5581.3    0.05       0
  5715.3    0.12       0  5722.6    0.05       0
Bank Sta=5006.7,5019.8
Exp/Cntr=0.3,0.1

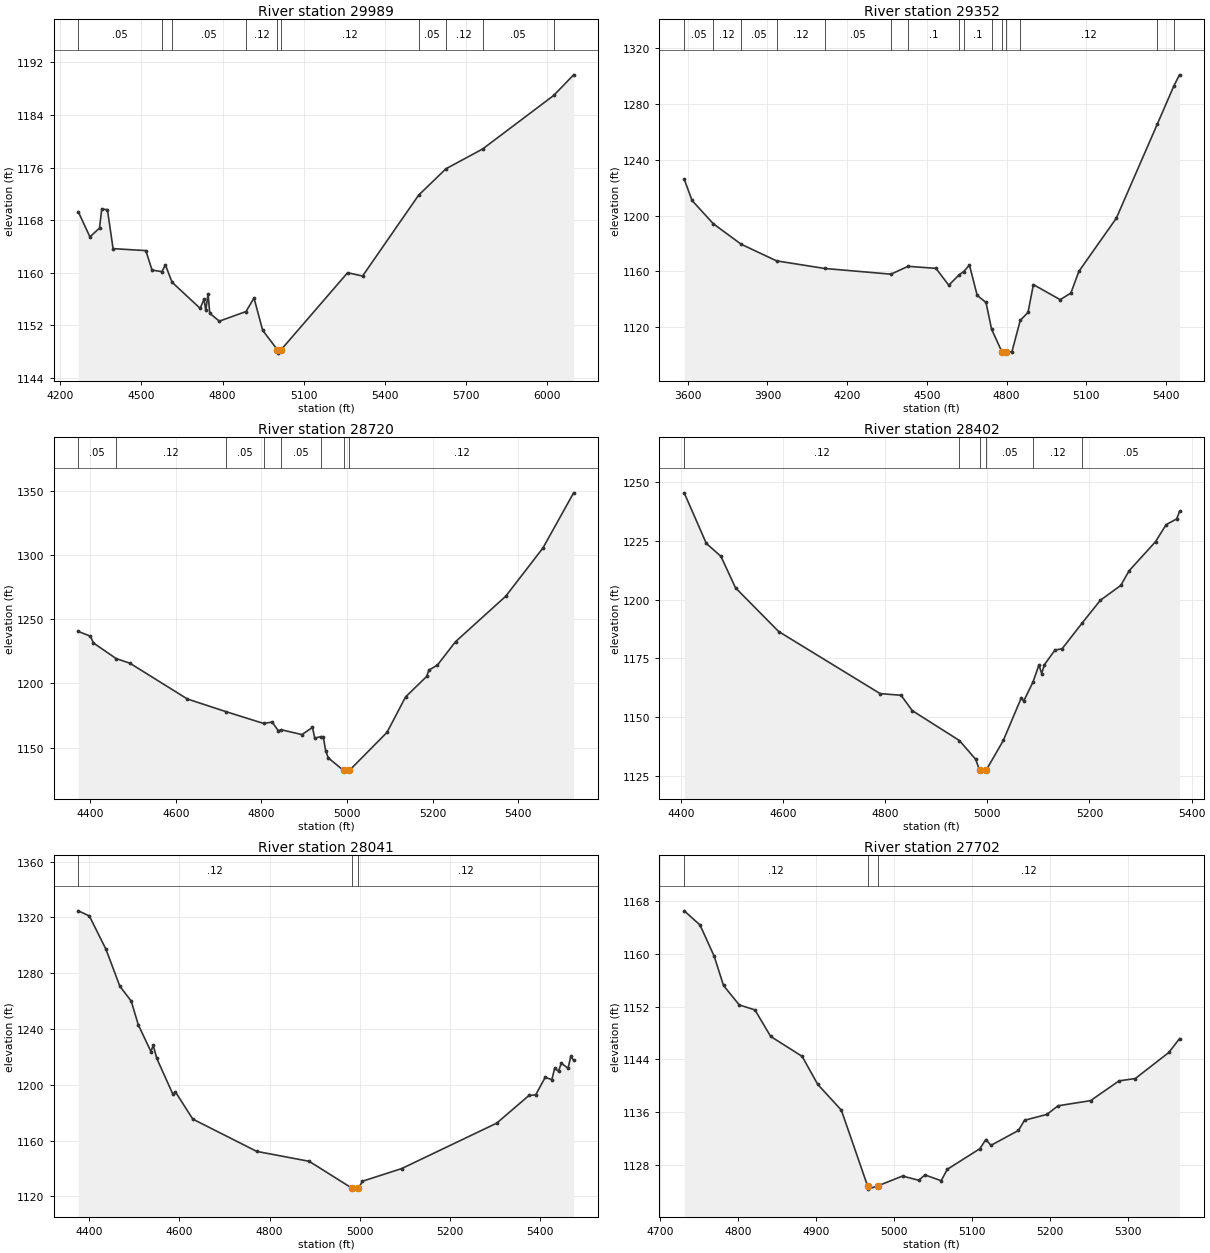
Type RM Length L Ch R = 1,29989,637,637,637
BEGIN DESCRIPTION:
BYRNES CREEK 52.0
END DESCRIPTION:
XS GIS Cut Line= 3
      2830155.67     10220453.10      2830660.64     10220822.48
      2831841.84     10221067.05
#Sta/Elev= 30
  4266.7 1169.27  4309.6 1165.46  4345.1 1166.80  4353.4 1169.70  4374.4 1169.59
  4395.3 1163.67  4516.5 1163.37  4539.3 1160.41  4576.0 1160.17  4588.9 1161.19
  4613.5 1158.56  4717.3 1154.59  4731.9 1155.99  4738.1 1154.27  4746.6 1156.80
  4752.8 1153.84  4788.3 1152.64  4887.1 1154.11  4916.5 1156.17  4948.6 1151.25
  5003.3 1148.28  5003.8 1147.78  5016.4 1148.28  5262.7 1160.01  5318.0 1159.50
  5525.3 1171.80  5626.6 1175.82  5762.0 1178.82  6025.1 1186.97  6098.6 1190.10
#Mann=10,-1,0
  4266.7    0.05       0  4576.0     0.1       0  4613.5    0.05       0
  4887.1    0.12       0  5003.3    0.07       0  5016.4    0.12       0
  5525.3    0.05       0  5626.6    0.12       0  5762.0    0.05       0
  6025.1    0.12       0
Bank Sta=5003.3,5016.4
Exp/Cntr=0.3,0.1

Type RM Length L Ch R = 1,29352,632,632,632
BEGIN DESCRIPTION:
BYRNES CREEK 51.0
END DESCRIPTION:
XS GIS Cut Line= 3
      2829327.28     10220335.49      2830327.31     10220739.15
      2830233.70     10221519.23
#Sta/Elev= 30
  3586.9 1226.09  3616.4 1210.86  3696.6 1194.14  3801.3 1179.49  3934.3 1167.59
  4115.3 1162.14  4365.0 1158.06  4429.3 1163.68  4534.3 1162.22  4582.5 1150.17
  4622.2 1157.70  4638.6 1159.91  4660.4 1164.59  4689.5 1142.86  4722.8 1137.76
  4743.6 1118.69  4783.6 1101.99  4784.1 1101.49  4796.8 1101.99  4820.4 1102.59
  4851.5 1124.90  4880.8 1130.71  4901.0 1150.60  5001.7 1139.79  5042.0 1144.47
  5072.2 1160.06  5213.2 1198.17  5368.1 1265.87  5430.1 1293.10  5451.0 1300.86
#Mann=15,-1,0
  3586.9    0.05       0  3696.6    0.12       0  3801.3    0.05       0
  3934.3    0.12       0  4115.3    0.05       0  4365.0    0.12       0
  4429.3     0.1       0  4622.2    0.05       0  4638.6     0.1       0
  4743.6    0.05       0  4783.6    0.07       0  4796.8    0.05       0
  4851.5    0.12       0  5368.1    0.05       0  5430.1    0.12       0
Bank Sta=4783.6,4796.8
Exp/Cntr=0.3,0.1

Type RM Length L Ch R = 1,28720,318,318,318
BEGIN DESCRIPTION:
BYRNES CREEK 50.0
END DESCRIPTION:
XS GIS Cut Line= 3
      2829355.69     10220503.11      2829742.82     10220856.42
      2829955.67     10221453.08
#Sta/Elev= 30
  4371.9 1240.42  4399.9 1236.77  4407.4 1231.40  4460.3 1219.32  4492.5 1215.70
  4626.9 1187.85  4717.6 1177.97  4805.0 1168.84  4824.9 1169.92  4839.1 1163.29
  4846.2 1163.94  4894.6 1160.18  4919.2 1165.77  4924.5 1157.44  4938.9 1158.60
  4944.7 1158.05  4950.0 1147.55  4956.2 1142.03  4992.0 1132.25  4992.5 1131.75
  5005.3 1132.25  5093.5 1161.97  5136.7 1189.44  5185.9 1205.37  5191.2 1210.34
  5211.0 1214.20  5253.5 1232.45  5370.7 1267.77  5457.8 1305.35  5529.5 1348.25
#Mann=8,-1,0
  4371.9    0.05       0  4460.3    0.12       0  4717.6    0.05       0
  4805.0    0.12       0  4846.2    0.05       0  4938.9    0.12       0
  4992.0    0.07       0  5005.3    0.12       0
Bank Sta=4992,5005.3
Exp/Cntr=0.3,0.1

Type RM Length L Ch R = 1,28402,361,361,361
BEGIN DESCRIPTION:
BYRNES CREEK 49.0
END DESCRIPTION:
XS GIS Cut Line= 3
      2829182.94     10220604.70      2829443.34     10220908.50
      2829590.59     10221458.50
#Sta/Elev= 30
  4406.8 1245.48  4450.1 1223.92  4478.7 1218.43  4507.2 1205.03  4591.7 1186.41
  4790.4 1159.96  4831.3 1159.27  4853.1 1152.73  4945.5 1139.99  4977.3 1132.00
  4984.8 1127.46  4985.3 1126.96  4998.1 1127.46  5031.5 1140.07  5066.3 1158.02
  5071.5 1156.92  5089.3 1164.80  5101.2 1172.21  5106.4 1168.52  5111.9 1172.31
  5132.6 1178.56  5146.4 1179.05  5186.3 1190.20  5221.3 1199.71  5261.3 1206.05
  5277.6 1212.29  5329.3 1224.67  5350.0 1231.92  5370.7 1234.37  5376.3 1237.55
#Mann=6,-1,0
  4406.8    0.12       0  4945.5    0.05       0  4984.8    0.05       0
  4998.1    0.05       0  5089.3    0.12       0  5186.3    0.05       0
Bank Sta=4984.8,4998.1
Exp/Cntr=0.3,0.1

Type RM Length L Ch R = 1,28041,339,339,339
BEGIN DESCRIPTION:
BYRNES CREEK 48.0
END DESCRIPTION:
XS GIS Cut Line= 3
      2829005.69     10220553.15      2829176.42     10221331.68
      2829346.77     10221579.67
#Sta/Elev= 30
  4376.1 1324.75  4400.5 1321.10  4437.5 1297.11  4468.2 1270.66  4493.3 1260.04
  4509.2 1242.89  4537.1 1223.78  4542.2 1228.31  4550.1 1218.85  4586.0 1193.03
  4591.2 1194.95  4629.9 1175.35  4771.6 1152.19  4887.9 1145.07  4983.6 1125.62
  4984.1 1125.12  4997.0 1125.62  5006.0 1130.80  5092.7 1139.84  5303.3 1172.41
  5375.0 1192.29  5389.9 1192.74  5410.9 1205.25  5425.8 1203.67  5431.8 1211.69
  5440.6 1209.75  5446.7 1215.45  5461.6 1211.84  5467.7 1220.32  5474.0 1217.55
#Mann=3,-1,0
  4376.1    0.12       0  4983.6    0.07       0  4997.0    0.12       0
Bank Sta=4983.6,4997
Exp/Cntr=0.3,0.1

Type RM Length L Ch R = 1,27702,468,468,468
BEGIN DESCRIPTION:
BYRNES CREEK 47.0
END DESCRIPTION:
XS GIS Cut Line= 3
      2828855.69     10220903.06      2828823.25     10221170.00
      2829055.68     10221453.11
#Sta/Elev= 30
  4731.1 1166.58  4751.3 1164.44  4769.5 1159.70  4781.5 1155.24  4801.7 1152.29
  4821.8 1151.53  4842.0 1147.50  4882.3 1144.48  4902.4 1140.21  4932.6 1136.31
  4966.2 1124.81  4966.7 1124.31  4979.6 1124.81  5011.1 1126.30  5031.9 1125.65
  5039.8 1126.47  5060.6 1125.59  5068.5 1127.32  5110.1 1130.44  5118.0 1131.84
  5124.5 1130.96  5159.7 1133.22  5167.5 1134.77  5196.2 1135.66  5210.6 1136.97
  5252.2 1137.75  5288.7 1140.75  5309.6 1141.11  5352.7 1145.08  5366.3 1147.17
#Mann=3,-1,0
  4731.1    0.12       0  4966.2    0.07       0  4979.6    0.12       0
Bank Sta=4966.2,4979.6
Exp/Cntr=0.3,0.1

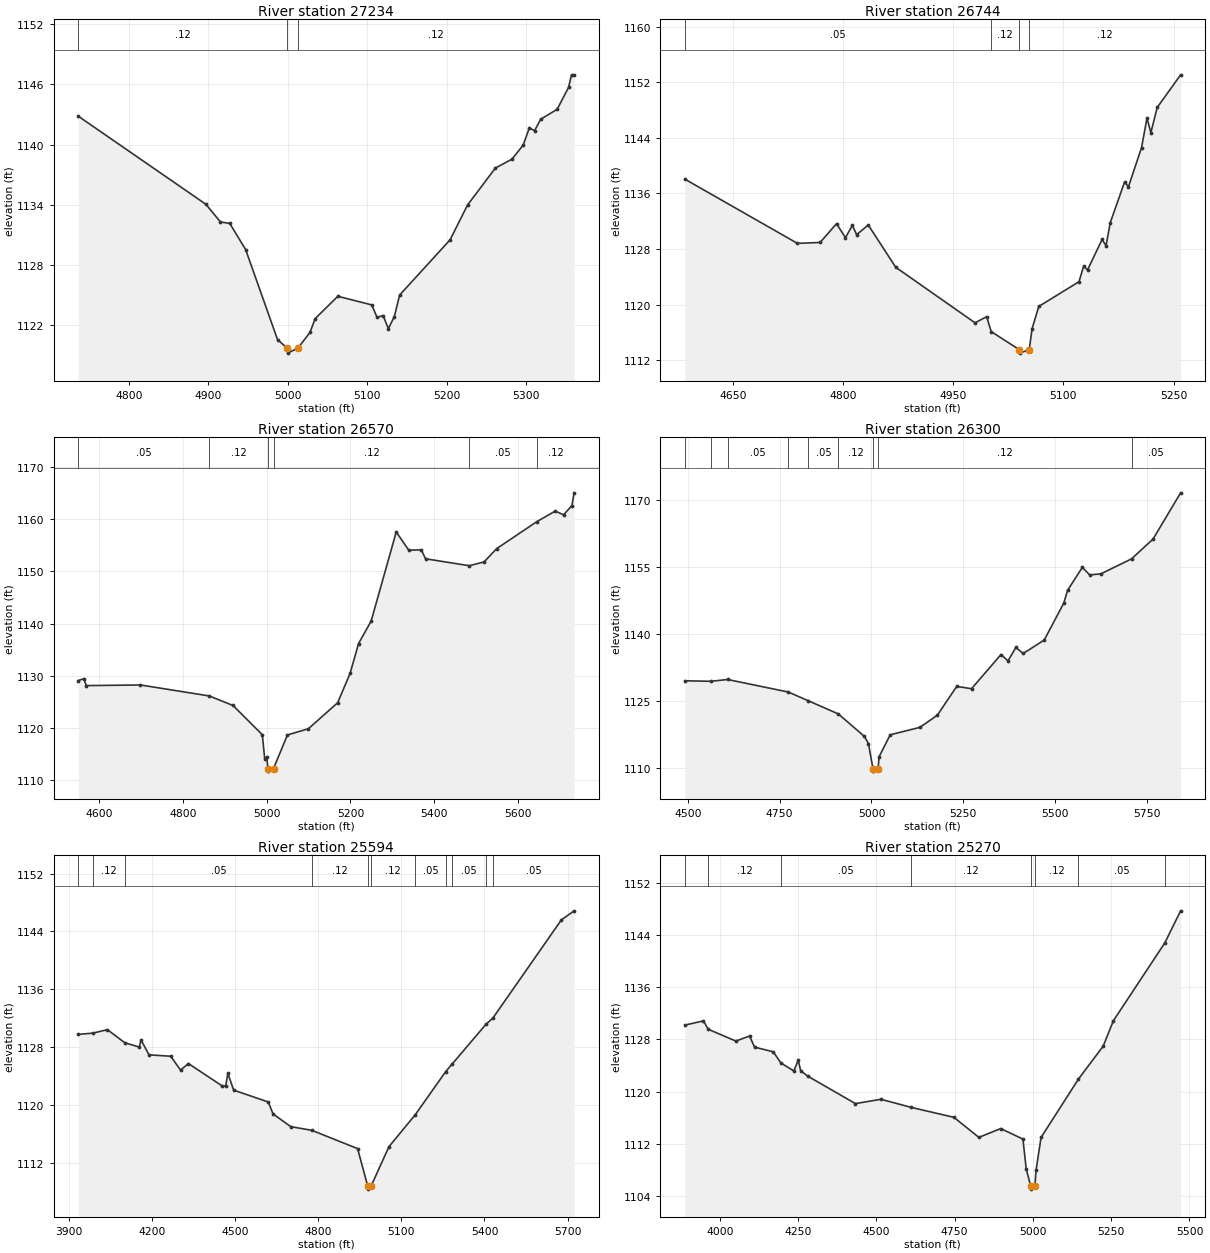
Type RM Length L Ch R = 1,27234,490,490,490
BEGIN DESCRIPTION:
BYRNES CREEK 46.0
END DESCRIPTION:
XS GIS Cut Line= 3
      2828505.69     10221053.09      2828484.00     10221316.00
      2828755.68     10221553.11
#Sta/Elev= 30
  4736.2 1142.82  4896.8 1134.04  4915.2 1132.27  4926.9 1132.13  4946.9 1129.52
  4987.1 1120.53  4999.3 1119.69  4999.8 1119.19  5012.7 1119.69  5027.9 1121.25
  5034.5 1122.64  5063.0 1124.86  5105.7 1124.00  5112.4 1122.75  5120.0 1122.94
  5126.6 1121.63  5134.2 1122.84  5140.8 1124.98  5204.4 1130.50  5226.3 1133.96
  5261.4 1137.65  5282.3 1138.54  5296.5 1139.95  5304.1 1141.65  5310.8 1141.38
  5318.4 1142.52  5339.2 1143.51  5353.5 1145.69  5357.3 1146.95  5360.6 1146.95
#Mann=3,-1,0
  4736.2    0.12       0  4999.3    0.07       0  5012.7    0.12       0
Bank Sta=4999.3,5012.7
Exp/Cntr=0.3,0.1

Type RM Length L Ch R = 1,26744,174,174,174
BEGIN DESCRIPTION:
BYRNES CREEK 45.0
END DESCRIPTION:
XS GIS Cut Line= 3
      2828105.67     10221353.09      2828311.75     10221714.00
      2828555.68     10221803.11
#Sta/Elev= 30
  4584.4 1138.07  4737.8 1128.82  4768.7 1128.95  4791.1 1131.66  4803.2 1129.63
  4812.7 1131.43  4818.4 1130.07  4834.3 1131.46  4871.7 1125.38  4979.7 1117.38
  4995.5 1118.27  5001.7 1116.12  5040.0 1113.52  5040.5 1113.02  5053.5 1113.52
  5057.4 1116.54  5066.5 1119.74  5121.3 1123.30  5127.6 1125.53  5132.9 1124.99
  5152.8 1129.39  5158.1 1128.48  5163.9 1131.81  5183.3 1137.63  5188.7 1136.98
  5206.5 1142.61  5213.9 1146.86  5219.2 1144.76  5227.8 1148.38  5259.7 1153.08
#Mann=4,-1,0
  4584.4    0.05       0  5001.7    0.12       0  5040.0    0.05       0
  5053.5    0.12       0
Bank Sta=5040,5053.5
Exp/Cntr=0.3,0.1

Type RM Length L Ch R = 1,26570,270,270,270
BEGIN DESCRIPTION:
BYRNES CREEK 44.0
END DESCRIPTION:
XS GIS Cut Line= 3
      2827892.40     10221770.39      2828126.79     10221884.98
      2829050.96     10221900.60
#Sta/Elev= 30
  4549.7 1129.10  4563.1 1129.46  4568.7 1128.13  4698.1 1128.25  4862.7 1126.15
  4919.5 1124.32  4989.5 1118.72  4995.2 1114.13  5000.2 1114.51  5002.8 1112.25
  5003.3 1111.75  5016.3 1112.25  5049.5 1118.68  5099.5 1119.86  5169.5 1124.84
  5199.5 1130.51  5219.5 1136.18  5249.6 1140.48  5309.6 1157.55  5339.6 1154.06
  5369.6 1154.14  5379.6 1152.42  5484.3 1151.09  5519.6 1151.82  5549.6 1154.36
  5645.5 1159.52  5689.6 1161.55  5709.6 1160.84  5729.6 1162.61  5734.9 1165.05
#Mann=6,-1,0
  4549.7    0.05       0  4862.7    0.12       0  5002.8    0.07       0
  5016.3    0.12       0  5484.3    0.05       0  5645.5    0.12       0
Bank Sta=5002.8,5016.3
Exp/Cntr=0.3,0.1

Type RM Length L Ch R = 1,26300,706,706,706
BEGIN DESCRIPTION:
Mapping XS 093da718
END DESCRIPTION:
XS GIS Cut Line= 3
      2827868.95     10221983.92      2828184.08     10222171.44
      2829161.93     10222070.01
#Sta/Elev= 30
  4491.9 1129.58  4563.3 1129.47  4608.3 1129.87  4773.7 1127.07  4828.6 1125.10
  4909.8 1122.18  4980.9 1117.15  4991.9 1115.54  5004.3 1109.90  5004.8 1109.40
  5017.8 1109.90  5021.1 1112.66  5051.2 1117.52  5131.7 1119.17  5179.3 1121.88
  5232.2 1128.33  5272.4 1127.81  5352.8 1135.45  5371.7 1134.03  5393.1 1137.02
  5413.2 1135.68  5470.4 1138.69  5523.8 1146.96  5533.8 1149.77  5574.2 1154.92
  5594.1 1153.24  5624.3 1153.46  5708.1 1156.82  5766.6 1161.24  5841.7 1171.57
#Mann=9,-1,0
  4491.9    0.05       0  4563.3    0.12       0  4608.3    0.05       0
  4773.7    0.12       0  4828.6    0.05       0  4909.8    0.12       0
  5004.3    0.07       0  5017.8    0.12       0  5708.1    0.05       0
Bank Sta=5004.3,5017.8
Exp/Cntr=0.3,0.1

Type RM Length L Ch R = 1,25594,324,324,324
BEGIN DESCRIPTION:
Mapping XS ad21bf9a
END DESCRIPTION:
XS GIS Cut Line= 4
      2827848.15     10222002.17      2828277.83     10222533.42
      2828582.51     10222890.19      2829031.83     10223342.10
#Sta/Elev= 30
  3934.1 1129.78  3986.2 1129.95  4039.1 1130.43  4102.0 1128.62  4154.0 1128.03
  4160.6 1128.99  4189.3 1126.95  4267.7 1126.76  4302.9 1124.85  4331.6 1125.75
  4451.6 1122.70  4466.0 1122.64  4473.9 1124.40  4494.7 1122.08  4619.6 1120.44
  4636.9 1118.79  4700.6 1117.04  4777.2 1116.52  4942.1 1114.00  4978.1 1108.90
  4978.6 1108.40  4991.8 1108.90  5055.2 1114.26  5150.1 1118.67  5260.3 1124.65
  5284.3 1125.72  5405.1 1131.16  5430.5 1132.04  5677.7 1145.60  5723.8 1146.85
#Mann=11,-1,0
  3934.1    0.05       0  3986.2    0.12       0  4102.0    0.05       0
  4777.2    0.12       0  4978.1    0.07       0  4991.8    0.12       0
  5150.1    0.05       0  5260.3    0.12       0  5284.3    0.05       0
  5405.1    0.12       0  5430.5    0.05       0
Bank Sta=4978.1,4991.8
Exp/Cntr=0.3,0.1

Type RM Length L Ch R = 1,25270,1346,1346,1346
BEGIN DESCRIPTION:
BYRNES CREEK 43.0
END DESCRIPTION:
XS GIS Cut Line= 3
      2827782.68     10222004.94      2828173.66     10222723.52
      2828405.70     10223453.16
#Sta/Elev= 30
  3888.0 1130.19  3947.6 1130.84  3962.9 1129.55  4051.1 1127.75  4094.8 1128.52
  4110.9 1126.82  4170.5 1126.11  4195.1 1124.39  4236.3 1123.18  4250.2 1124.83
  4258.2 1123.21  4280.0 1122.40  4432.9 1118.18  4514.6 1118.84  4612.0 1117.59
  4747.6 1116.08  4827.3 1113.01  4897.0 1114.36  4968.0 1112.75  4978.5 1108.19
  4992.6 1105.59  4993.1 1105.09  5006.3 1105.59  5009.9 1107.97  5025.9 1113.00
  5145.5 1121.94  5224.6 1126.99  5256.9 1130.86  5420.9 1142.75  5471.7 1147.68
#Mann=8,-1,0
  3888.0    0.05       0  3962.9    0.12       0  4195.1    0.05       0
  4612.0    0.12       0  4992.6    0.07       0  5006.3    0.12       0
  5145.5    0.05       0  5420.9    0.12       0
Bank Sta=4992.6,5006.3
Exp/Cntr=0.3,0.1

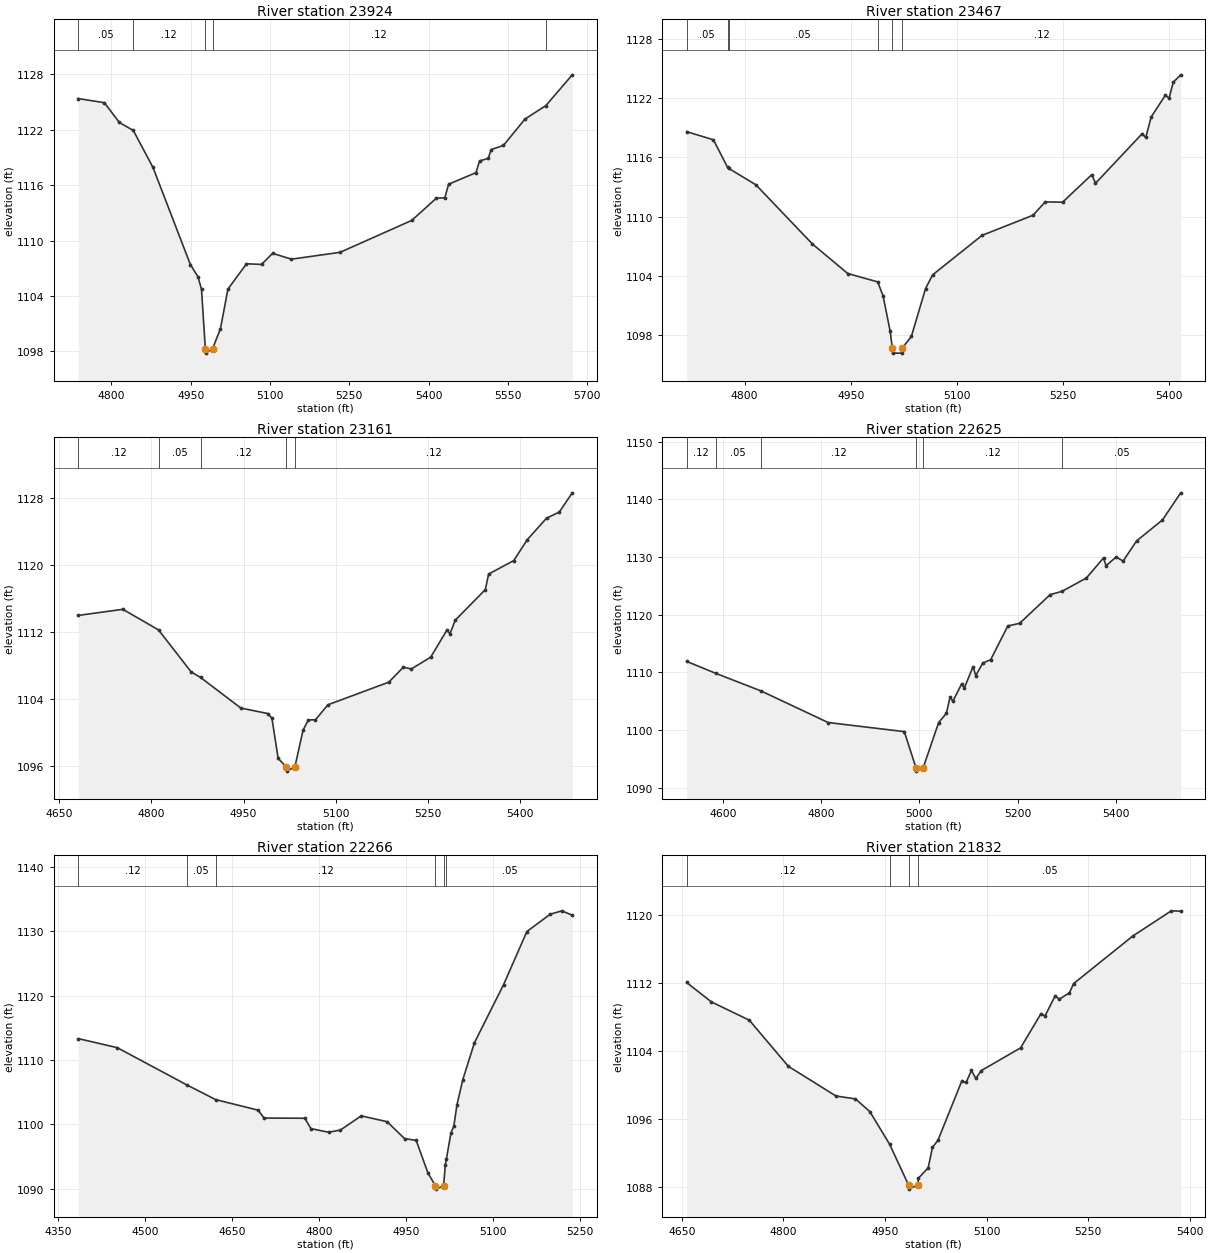
Type RM Length L Ch R = 1,23924,457,457,457
BEGIN DESCRIPTION:
BYRNES CREEK 42.0
END DESCRIPTION:
XS GIS Cut Line= 3
      2827095.91     10222573.23      2827499.55     10223015.93
      2827805.73     10223153.13
#Sta/Elev= 30
  4737.3 1125.39  4786.7 1124.94  4815.1 1122.80  4841.5 1121.93  4878.6 1117.94
  4949.5 1107.40  4963.7 1106.10  4970.5 1104.72  4977.7 1098.31  4978.2 1097.81
  4991.6 1098.31  5006.3 1100.45  5020.5 1104.75  5055.6 1107.49  5084.0 1107.42
  5104.9 1108.62  5140.7 1107.99  5232.6 1108.73  5368.3 1112.19  5414.7 1114.59
  5430.8 1114.64  5437.9 1116.11  5489.7 1117.36  5496.5 1118.63  5512.9 1118.91
  5518.4 1119.86  5541.6 1120.31  5582.5 1123.17  5622.0 1124.63  5671.9 1127.96
#Mann=5,-1,0
  4737.3    0.05       0  4841.5    0.12       0  4977.7    0.07       0
  4991.6    0.12       0  5622.0    0.05       0
Bank Sta=4977.7,4991.6
Exp/Cntr=0.3,0.1

Type RM Length L Ch R = 1,23467,306,306,306
BEGIN DESCRIPTION:
BYRNES CREEK 41.0
END DESCRIPTION:
XS GIS Cut Line= 3
      2827017.81     10223167.84      2827456.98     10223177.96
      2827705.69     10223253.11
#Sta/Elev= 30
  4718.0 1118.60  4755.9 1117.77  4775.9 1114.98  4777.5 1114.88  4815.9 1113.22
  4895.9 1107.23  4945.9 1104.24  4988.3 1103.39  4995.9 1101.98  5006.0 1098.38
  5009.0 1096.68  5009.5 1096.18  5022.4 1096.18  5022.9 1096.68  5036.0 1097.87
  5056.0 1102.71  5066.0 1104.10  5136.0 1108.10  5208.2 1110.14  5225.4 1111.49
  5250.0 1111.46  5291.3 1114.25  5296.5 1113.37  5362.4 1118.38  5367.7 1118.01
  5375.3 1120.08  5395.4 1122.29  5400.6 1121.98  5406.6 1123.61  5417.1 1124.35
#Mann=6,-1,0
  4718.0    0.05       0  4775.9    0.12       0  4777.5    0.05       0
  4988.3    0.12       0  5009.0    0.07       0  5022.9    0.12       0
Bank Sta=5009,5022.9
Exp/Cntr=0.3,0.1

Type RM Length L Ch R = 1,23161,536,536,536
BEGIN DESCRIPTION:
BYRNES CREEK 40.0
END DESCRIPTION:
XS GIS Cut Line= 3
      2827023.93     10223520.82      2827516.53     10223451.37
      2827805.72     10223353.10
#Sta/Elev= 30
  4681.4 1113.95  4753.9 1114.68  4811.9 1112.22  4864.9 1107.21  4880.2 1106.55
  4945.7 1102.90  4989.3 1102.25  4996.2 1101.69  5006.3 1096.89  5019.6 1095.88
  5020.1 1095.38  5033.5 1095.88  5046.7 1100.25  5055.4 1101.49  5066.9 1101.50
  5087.1 1103.29  5186.1 1105.99  5209.7 1107.77  5222.8 1107.57  5254.2 1108.97
  5280.3 1112.17  5285.6 1111.79  5294.2 1113.39  5343.0 1117.03  5348.3 1118.88
  5389.2 1120.49  5411.1 1122.98  5442.5 1125.55  5463.1 1126.27  5484.3 1128.57
#Mann=5,-1,0
  4681.4    0.12       0  4811.9    0.05       0  4880.2    0.12       0
  5019.6    0.07       0  5033.5    0.12       0
Bank Sta=5019.6,5033.5
Exp/Cntr=0.3,0.1

Type RM Length L Ch R = 1,22625,359,359,359
BEGIN DESCRIPTION:
Mapping XS 99c169b2
END DESCRIPTION:
XS GIS Cut Line= 4
      2827123.74     10223631.50      2827299.52     10223930.98
      2827536.06     10224035.14      2827922.59     10224138.79
#Sta/Elev= 30
  4526.2 1111.89  4585.2 1109.83  4677.2 1106.78  4814.3 1101.29  4969.3 1099.71
  4993.4 1093.36  4993.9 1092.86  5007.4 1093.36  5039.3 1101.29  5055.0 1102.89
  5062.7 1105.77  5068.1 1104.96  5086.0 1107.98  5091.5 1107.27  5109.3 1110.99
  5114.8 1109.43  5129.0 1111.59  5145.2 1112.20  5180.1 1118.04  5204.0 1118.49
  5266.1 1123.46  5290.6 1124.05  5340.1 1126.36  5374.9 1129.84  5380.1 1128.49
  5400.7 1130.00  5414.9 1129.29  5442.1 1132.78  5495.0 1136.43  5532.1 1141.13
#Mann=6,-1,0
  4526.2    0.12       0  4585.2    0.05       0  4677.2    0.12       0
  4993.4    0.07       0  5007.4    0.12       0  5290.6    0.05       0
Bank Sta=4993.4,5007.4
Exp/Cntr=0.3,0.1

Type RM Length L Ch R = 1,22266,434,434,434
BEGIN DESCRIPTION:
BYRNES CREEK 39.0
END DESCRIPTION:
XS GIS Cut Line= 3
      2827079.59     10223596.56      2827155.09     10224079.44
      2827190.81     10224441.03
#Sta/Elev= 30
  4384.1 1113.32  4451.2 1111.92  4571.3 1106.14  4620.9 1103.86  4694.4 1102.21
  4704.5 1100.99  4774.9 1100.96  4785.5 1099.35  4815.8 1098.79  4836.1 1099.12
  4872.2 1101.33  4916.7 1100.43  4946.9 1097.80  4967.0 1097.52  4987.1 1092.50
  5000.2 1090.46  5000.7 1089.96  5014.2 1090.46  5017.2 1093.66  5019.1 1094.64
  5026.9 1098.67  5031.9 1099.74  5037.3 1103.04  5047.4 1106.95  5067.5 1112.69
  5117.7 1121.69  5157.9 1129.94  5198.1 1132.62  5218.2 1133.15  5236.2 1132.47
#Mann=6,-1,0
  4384.1    0.12       0  4571.3    0.05       0  4620.9    0.12       0
  5000.2    0.07       0  5014.2    0.12       0  5019.1    0.05       0
Bank Sta=5000.2,5014.2
Exp/Cntr=0.3,0.1

Type RM Length L Ch R = 1,21832,334,334,334
BEGIN DESCRIPTION:
BYRNES CREEK 38.0
END DESCRIPTION:
XS GIS Cut Line= 3
      2827065.49     10223662.10      2826769.67     10224030.83
      2826911.37     10224245.09
#Sta/Elev= 30
  4657.2 1112.08  4693.7 1109.79  4749.7 1107.63  4807.3 1102.19  4877.7 1098.68
  4906.5 1098.34  4927.7 1096.84  4956.8 1093.00  4984.8 1088.19  4985.3 1087.69
  4998.8 1088.19  4999.4 1088.98  5013.8 1090.19  5020.2 1092.62  5028.2 1093.44
  5063.4 1100.43  5069.8 1100.28  5077.8 1101.70  5084.2 1100.75  5092.2 1101.68
  5150.3 1104.36  5180.4 1108.40  5186.4 1108.13  5201.4 1110.51  5207.4 1110.11
  5222.5 1110.86  5228.6 1111.95  5315.8 1117.55  5372.9 1120.54  5386.8 1120.50
#Mann=4,-1,0
  4657.2    0.12       0  4956.8    0.05       0  4984.8    0.03       0
  4998.8    0.05       0
Bank Sta=4984.8,4998.8
Exp/Cntr=0.3,0.1