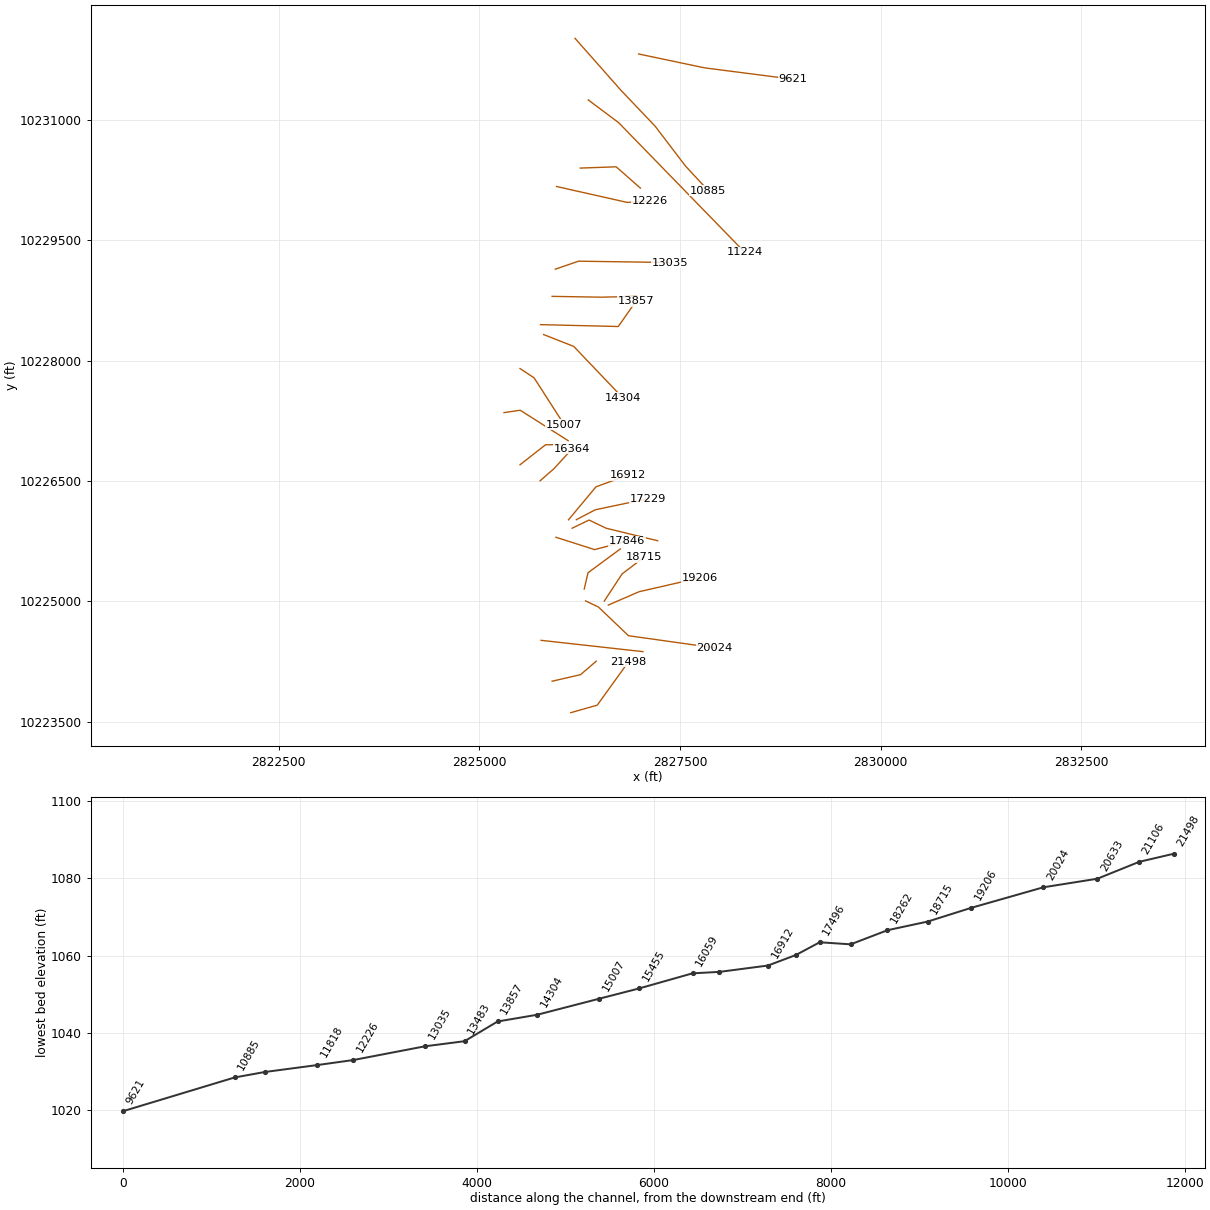
HEC-RAS study BYRNES CREEK.prj: BYRNES CREEK Base Level Engineering

--- BYRNES CREEK.g01 (geometry) --- (continued)

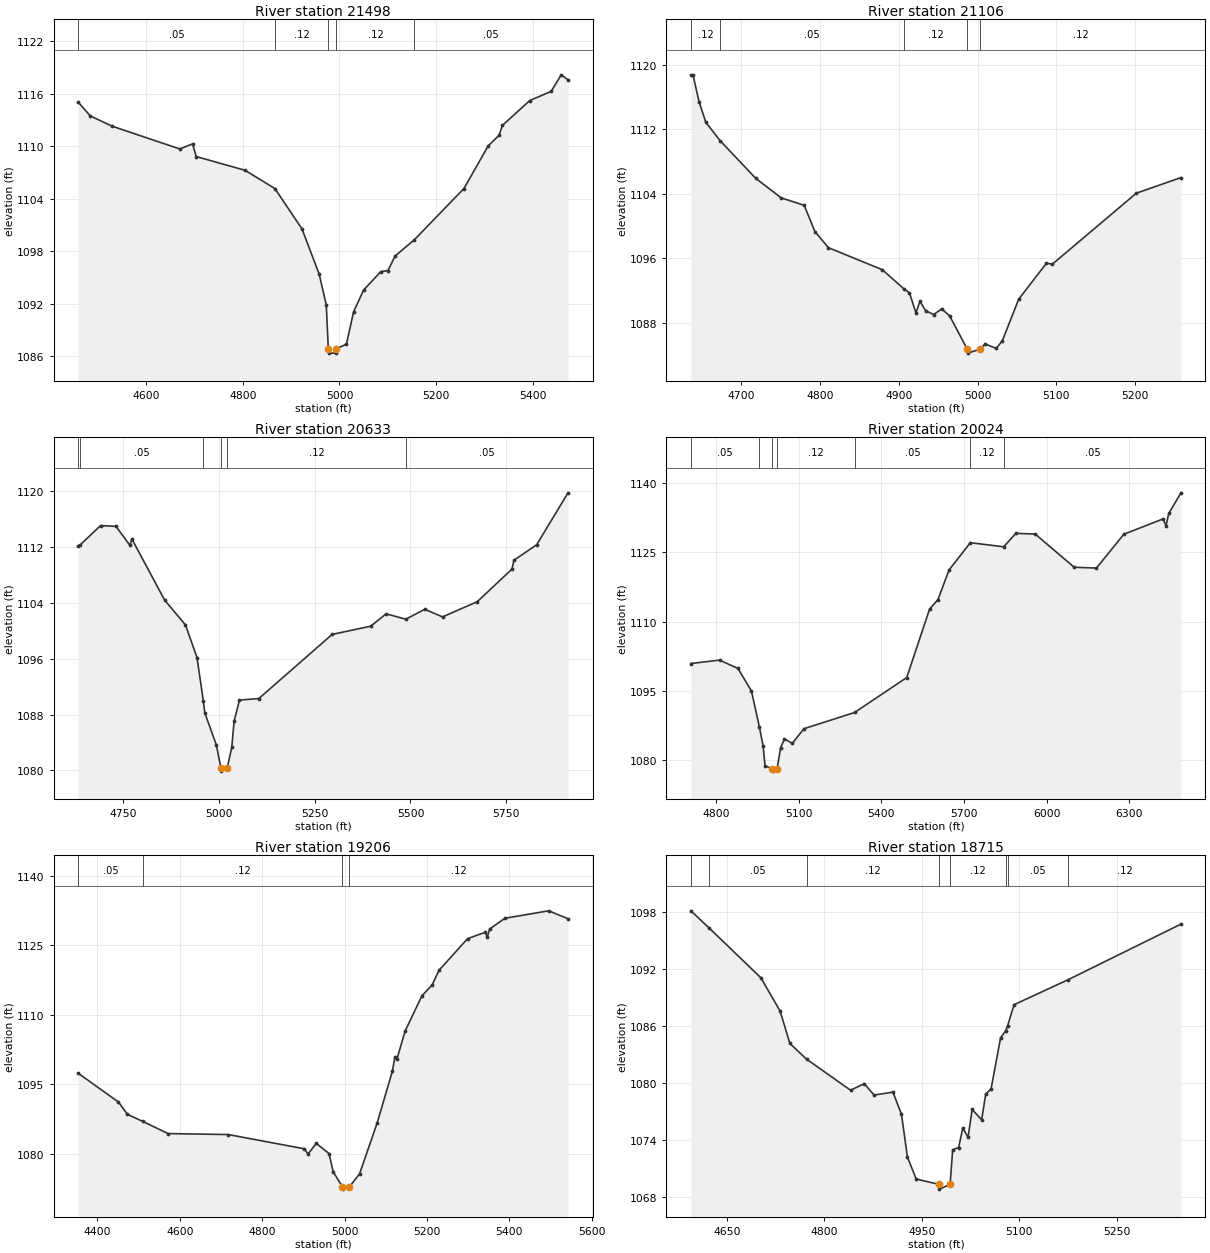
Type RM Length L Ch R = 1,21498,392,392,392
BEGIN DESCRIPTION:
BYRNES CREEK 37.0
END DESCRIPTION:
XS GIS Cut Line= 3
      2826137.77     10223610.70      2826467.59     10223704.44
      2826859.40     10224248.81
#Sta/Elev= 30
  4459.2 1115.05  4484.7 1113.46  4529.8 1112.29  4669.7 1109.69  4696.1 1110.27
  4703.6 1108.82  4804.3 1107.26  4866.4 1105.17  4922.4 1100.56  4958.0 1095.39
  4972.7 1091.86  4976.9 1086.86  4977.4 1086.36  4993.1 1086.36  4993.6 1086.86
  5014.4 1087.39  5029.2 1091.07  5050.0 1093.58  5085.6 1095.67  5100.3 1095.80
  5115.1 1097.46  5155.0 1099.32  5257.5 1105.17  5307.8 1110.05  5330.2 1111.26
  5337.2 1112.39  5393.7 1115.22  5437.9 1116.27  5458.7 1118.16  5472.8 1117.59
#Mann=5,-1,0
  4459.2    0.05       0  4866.4    0.12       0  4976.9    0.07       0
  4993.6    0.12       0  5155.0    0.05       0
Bank Sta=4976.9,4993.6
Exp/Cntr=0.3,0.1

Type RM Length L Ch R = 1,21106,473,473,473
BEGIN DESCRIPTION:
BYRNES CREEK 36.0
END DESCRIPTION:
XS GIS Cut Line= 3
      2825905.64     10224003.10      2826260.00     10224085.00
      2826455.70     10224253.12
#Sta/Elev= 30
  4636.3 1118.76  4638.9 1118.76  4646.6 1115.43  4655.1 1112.90  4673.4 1110.59
  4718.5 1105.93  4750.9 1103.50  4780.0 1102.59  4793.6 1099.33  4810.8 1097.33
  4879.1 1094.60  4906.3 1092.25  4913.5 1091.74  4921.8 1089.25  4926.9 1090.69
  4934.0 1089.52  4944.3 1089.04  4954.5 1089.75  4964.5 1088.88  4986.9 1084.76
  4987.4 1084.26  5003.6 1084.76  5009.4 1085.40  5023.7 1084.85  5031.4 1085.79
  5052.2 1090.95  5087.3 1095.39  5095.0 1095.30  5201.5 1104.09  5258.0 1106.02
#Mann=5,-1,0
  4636.3    0.12       0  4673.4    0.05       0  4906.3    0.12       0
  4986.9    0.07       0  5003.6    0.12       0
Bank Sta=4986.9,5003.6
Exp/Cntr=0.3,0.1

Type RM Length L Ch R = 1,20633,609,609,609
BEGIN DESCRIPTION:
Mapping XS b79b827a
END DESCRIPTION:
XS GIS Cut Line= 2
      2825767.35     10224513.16      2827036.94     10224372.10
#Sta/Elev= 30
  4633.3 1112.16  4639.6 1112.33  4692.0 1115.06  4732.2 1114.95  4768.5 1112.23
  4773.6 1113.14  4859.1 1104.38  4913.3 1100.84  4943.5 1096.15  4959.9 1089.96
  4963.7 1088.25  4993.8 1083.65  5005.6 1080.39  5006.1 1079.89  5022.4 1080.39
  5034.1 1083.30  5040.2 1087.04  5054.2 1090.07  5104.5 1090.28  5295.7 1099.47
  5396.3 1100.65  5436.5 1102.42  5487.7 1101.65  5537.2 1103.07  5583.5 1101.98
  5674.1 1104.16  5764.6 1108.83  5769.6 1110.09  5828.9 1112.31  5910.7 1119.75
#Mann=6,-1,0
  4633.3    0.12       0  4639.6    0.05       0  4959.9    0.12       0
  5005.6    0.07       0  5022.4    0.12       0  5487.7    0.05       0
Bank Sta=5005.6,5022.4
Exp/Cntr=0.3,0.1

Type RM Length L Ch R = 1,20024,818,818,818
BEGIN DESCRIPTION:
Mapping XS 0dba4c47
END DESCRIPTION:
XS GIS Cut Line= 4
      2826321.88     10225005.33      2826484.08     10224927.53
      2826856.48     10224570.76      2827929.39     10224419.72
#Sta/Elev= 30
  4708.7 1100.97  4812.5 1101.71  4879.3 1099.91  4928.3 1095.04  4957.2 1087.26
  4970.7 1083.17  4977.7 1078.84  5004.8 1078.18  5005.3 1077.68  5021.6 1078.18
  5034.3 1082.76  5048.4 1084.63  5076.7 1083.70  5119.2 1086.86  5302.9 1090.37
  5492.2 1097.93  5575.2 1112.74  5605.5 1114.79  5645.9 1121.21  5723.1 1127.12
  5844.5 1126.23  5888.2 1129.14  5958.9 1128.98  6100.3 1121.80  6181.1 1121.63
  6280.6 1128.95  6423.0 1132.26  6433.6 1130.78  6443.7 1133.44  6487.8 1137.91
#Mann=7,-1,0
  4708.7    0.05       0  4957.2    0.12       0  5004.8    0.07       0
  5021.6    0.12       0  5302.9    0.05       0  5723.1    0.12       0
  5844.5    0.05       0
Bank Sta=5004.8,5021.6
Exp/Cntr=0.3,0.1

Type RM Length L Ch R = 1,19206,491,491,491
BEGIN DESCRIPTION:
BYRNES CREEK 33.0
END DESCRIPTION:
XS GIS Cut Line= 3
      2826605.66     10224953.10      2826988.38     10225119.16
      2827741.31     10225291.98
#Sta/Elev= 30
  4353.0 1097.40  4451.1 1091.17  4472.9 1088.51  4510.3 1086.97  4571.5 1084.35
  4717.8 1084.14  4902.8 1081.06  4911.1 1079.93  4931.6 1082.22  4962.4 1080.04
  4972.6 1076.07  4995.0 1072.85  4995.5 1072.35  5011.9 1072.85  5036.5 1075.64
  5079.4 1086.68  5116.3 1097.84  5122.3 1100.86  5127.4 1100.46  5147.0 1106.47
  5188.1 1114.14  5213.1 1116.49  5229.1 1119.59  5298.9 1126.46  5341.7 1127.83
  5346.9 1126.83  5352.2 1128.53  5389.7 1130.87  5495.9 1132.47  5542.7 1130.76
#Mann=4,-1,0
  4353.0    0.05       0  4510.3    0.12       0  4995.0    0.07       0
  5011.9    0.12       0
Bank Sta=4995,5011.9
Exp/Cntr=0.3,0.1

Type RM Length L Ch R = 1,18715,453,453,453
BEGIN DESCRIPTION:
BYRNES CREEK 32.0
END DESCRIPTION:
XS GIS Cut Line= 3
      2826555.66     10225003.08      2826777.75     10225342.00
      2827055.67     10225553.10
#Sta/Elev= 30
  4594.8 1098.13  4623.3 1096.29  4702.4 1091.08  4732.0 1087.58  4747.1 1084.16
  4772.8 1082.50  4840.5 1079.23  4861.6 1079.92  4876.7 1078.72  4905.7 1079.03
  4918.9 1076.70  4928.0 1072.20  4941.6 1069.87  4976.8 1069.31  4977.3 1068.81
  4993.7 1069.31  4997.7 1072.97  5006.9 1073.19  5013.2 1075.24  5021.4 1074.29
  5027.7 1077.20  5042.3 1076.11  5048.5 1078.81  5056.8 1079.38  5071.4 1084.74
  5079.4 1085.51  5082.1 1085.98  5092.2 1088.24  5175.3 1090.87  5349.0 1096.73
#Mann=8,-1,0
  4594.8    0.12       0  4623.3    0.05       0  4772.8    0.12       0
  4976.8    0.05       0  4993.7    0.12       0  5079.4    0.12       0
  5082.1    0.05       0  5175.3    0.12       0
Bank Sta=4976.8,4993.7
Exp/Cntr=0.3,0.1

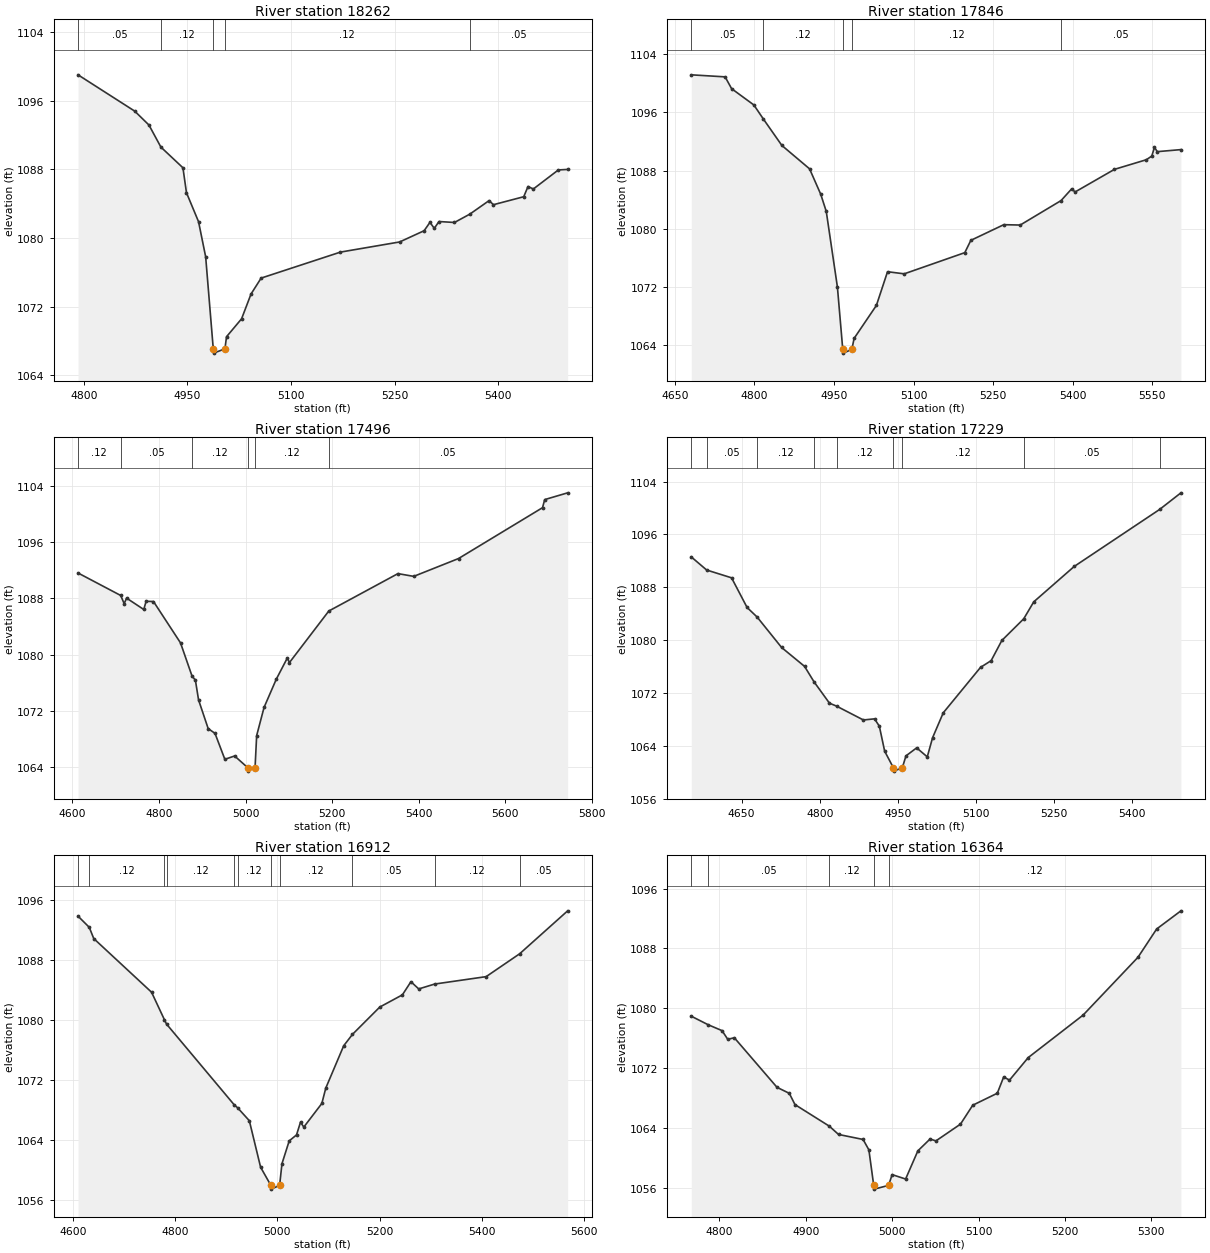
Type RM Length L Ch R = 1,18262,416,416,416
BEGIN DESCRIPTION:
BYRNES CREEK 31.0
END DESCRIPTION:
XS GIS Cut Line= 3
      2826305.68     10225153.09      2826352.75     10225356.00
      2826755.66     10225653.09
#Sta/Elev= 30
  4791.7 1099.00  4873.8 1094.77  4894.4 1093.15  4911.7 1090.58  4943.6 1088.17
  4948.7 1085.27  4966.2 1081.89  4976.5 1077.80  4987.5 1067.08  4988.0 1066.58
  5004.4 1067.08  5006.7 1068.49  5028.5 1070.58  5042.2 1073.47  5056.8 1075.32
  5171.7 1078.35  5257.3 1079.53  5292.8 1080.84  5301.2 1081.81  5307.5 1081.12
  5314.3 1081.91  5336.7 1081.80  5358.9 1082.77  5386.9 1084.35  5393.1 1083.87
  5437.0 1084.80  5443.2 1085.99  5450.9 1085.70  5487.1 1087.92  5500.6 1087.98
#Mann=5,-1,0
  4791.7    0.05       0  4911.7    0.12       0  4987.5    0.07       0
  5004.4    0.12       0  5358.9    0.05       0
Bank Sta=4987.5,5004.4
Exp/Cntr=0.3,0.1

Type RM Length L Ch R = 1,17846,350,350,350
BEGIN DESCRIPTION:
Mapping XS 5c9a39d7
END DESCRIPTION:
XS GIS Cut Line= 3
      2825953.30     10225798.61      2826435.04     10225644.54
      2826838.69     10225750.88
#Sta/Elev= 30
  4681.0 1101.15  4744.8 1100.87  4757.0 1099.25  4799.0 1097.01  4816.9 1095.08
  4851.8 1091.45  4904.0 1088.24  4925.0 1084.76  4935.5 1082.39  4956.5 1072.01
  4966.6 1063.43  4967.1 1062.93  4983.7 1063.43  4988.0 1064.96  5030.0 1069.48
  5051.0 1074.11  5082.5 1073.82  5196.7 1076.73  5208.1 1078.42  5270.2 1080.57
  5301.2 1080.52  5378.2 1083.88  5398.3 1085.50  5404.6 1085.06  5478.9 1088.17
  5539.0 1089.49  5549.2 1089.99  5554.3 1091.18  5559.7 1090.60  5604.2 1090.88
#Mann=5,-1,0
  4681.0    0.05       0  4816.9    0.12       0  4966.6    0.07       0
  4983.7    0.12       0  5378.2    0.05       0
Bank Sta=4966.6,4983.7
Exp/Cntr=0.3,0.1

Type RM Length L Ch R = 1,17496,267,267,267
BEGIN DESCRIPTION:
BYRNES CREEK 30.0
END DESCRIPTION:
XS GIS Cut Line= 4
      2826155.08     10225911.46      2826365.59     10226013.46
      2826578.27     10225911.47      2827220.65     10225755.21
#Sta/Elev= 30
  4612.9 1091.59  4711.4 1088.40  4719.5 1087.24  4725.1 1088.02  4764.7 1086.41
  4770.2 1087.57  4787.2 1087.54  4849.6 1081.67  4876.2 1076.96  4884.0 1076.37
  4891.3 1073.57  4913.5 1069.50  4929.3 1068.82  4952.0 1065.14  4974.6 1065.61
  5004.7 1063.96  5005.2 1063.46  5021.8 1063.96  5025.5 1068.51  5042.6 1072.51
  5070.8 1076.51  5096.2 1079.51  5101.3 1078.88  5192.1 1086.19  5351.8 1091.50
  5388.3 1091.11  5491.7 1093.64  5685.7 1100.86  5690.8 1102.01  5743.8 1102.97
#Mann=6,-1,0
  4612.9    0.12       0  4711.4    0.05       0  4876.2    0.12       0
  5004.7    0.07       0  5021.8    0.12       0  5192.1    0.05       0
Bank Sta=5004.7,5021.8
Exp/Cntr=0.3,0.1

Type RM Length L Ch R = 1,17229,317,317,317
BEGIN DESCRIPTION:
BYRNES CREEK 29.0
END DESCRIPTION:
XS GIS Cut Line= 3
      2826207.16     10226017.80      2826443.72     10226141.50
      2827102.04     10226280.10
#Sta/Elev= 30
  4553.5 1092.60  4583.0 1090.62  4630.8 1089.44  4660.6 1084.95  4679.9 1083.50
  4726.8 1078.90  4770.9 1076.04  4788.9 1073.72  4818.7 1070.47  4832.2 1070.03
  4883.8 1067.93  4905.2 1068.10  4914.4 1066.99  4924.6 1063.21  4941.4 1060.69
  4941.9 1060.19  4958.5 1060.69  4965.5 1062.50  4986.0 1063.71  5006.4 1062.35
  5016.6 1065.25  5037.1 1069.02  5108.6 1075.89  5129.0 1076.91  5149.5 1079.96
  5191.5 1083.24  5210.8 1085.81  5288.4 1091.16  5452.2 1099.78  5493.2 1102.30
#Mann=9,-1,0
  4553.5    0.12       0  4583.0    0.05       0  4679.9    0.12       0
  4788.9    0.05       0  4832.2    0.12       0  4941.4    0.07       0
  4958.5    0.12       0  5191.5    0.05       0  5452.2    0.12       0
Bank Sta=4941.4,4958.5
Exp/Cntr=0.3,0.1

Type RM Length L Ch R = 1,16912,548,548,548
BEGIN DESCRIPTION:
BYRNES CREEK 28.0
END DESCRIPTION:
XS GIS Cut Line= 3
      2826109.43     10226016.35      2826452.40     10226427.96
      2826849.55     10226573.37
#Sta/Elev= 30
  4609.6 1093.87  4631.6 1092.38  4640.4 1090.88  4753.6 1083.72  4778.7 1080.06
  4782.9 1079.47  4915.5 1068.69  4922.1 1068.30  4945.0 1066.58  4967.1 1060.37
  4987.2 1057.95  4987.7 1057.45  5004.3 1057.95  5008.9 1060.84  5023.1 1063.89
  5037.4 1064.68  5045.2 1066.38  5051.7 1065.73  5087.0 1068.88  5094.7 1070.93
  5129.8 1076.58  5147.0 1078.10  5200.4 1081.74  5244.7 1083.37  5261.4 1085.12
  5276.7 1084.16  5307.8 1084.81  5408.7 1085.80  5474.3 1088.85  5568.3 1094.58
#Mann=11,-1,0
  4609.6    0.05       0  4631.6    0.12       0  4778.7    0.05       0
  4782.9    0.12       0  4915.5    0.05       0  4922.1    0.12       0
  4987.2    0.07       0  5004.3    0.12       0  5147.0    0.05       0
  5307.8    0.12       0  5474.3    0.05       0
Bank Sta=4987.2,5004.3
Exp/Cntr=0.3,0.1

Type RM Length L Ch R = 1,16364,305,305,305
BEGIN DESCRIPTION:
BYRNES CREEK 27.0
END DESCRIPTION:
XS GIS Cut Line= 3
      2825755.71     10226503.13      2825930.75     10226656.00
      2826155.71     10226903.14
#Sta/Elev= 30
  4767.6 1078.93  4787.1 1077.79  4803.2 1077.00  4809.8 1075.84  4817.4 1076.05
  4866.8 1069.42  4881.0 1068.62  4887.6 1067.11  4927.3 1064.23  4938.0 1063.12
  4966.4 1062.45  4973.1 1061.06  4978.7 1056.31  4979.2 1055.81  4995.9 1056.31
  5000.0 1057.75  5015.6 1057.16  5029.8 1060.93  5043.9 1062.51  5050.7 1062.26
  5079.1 1064.50  5093.3 1067.03  5121.7 1068.63  5129.1 1070.81  5135.8 1070.38
  5157.5 1073.40  5221.0 1079.08  5284.5 1086.81  5306.1 1090.59  5334.2 1093.02
#Mann=5,-1,0
  4767.6    0.12       0  4787.1    0.05       0  4927.3    0.12       0
  4978.7    0.07       0  4995.9    0.12       0
Bank Sta=4978.7,4995.9
Exp/Cntr=0.3,0.1

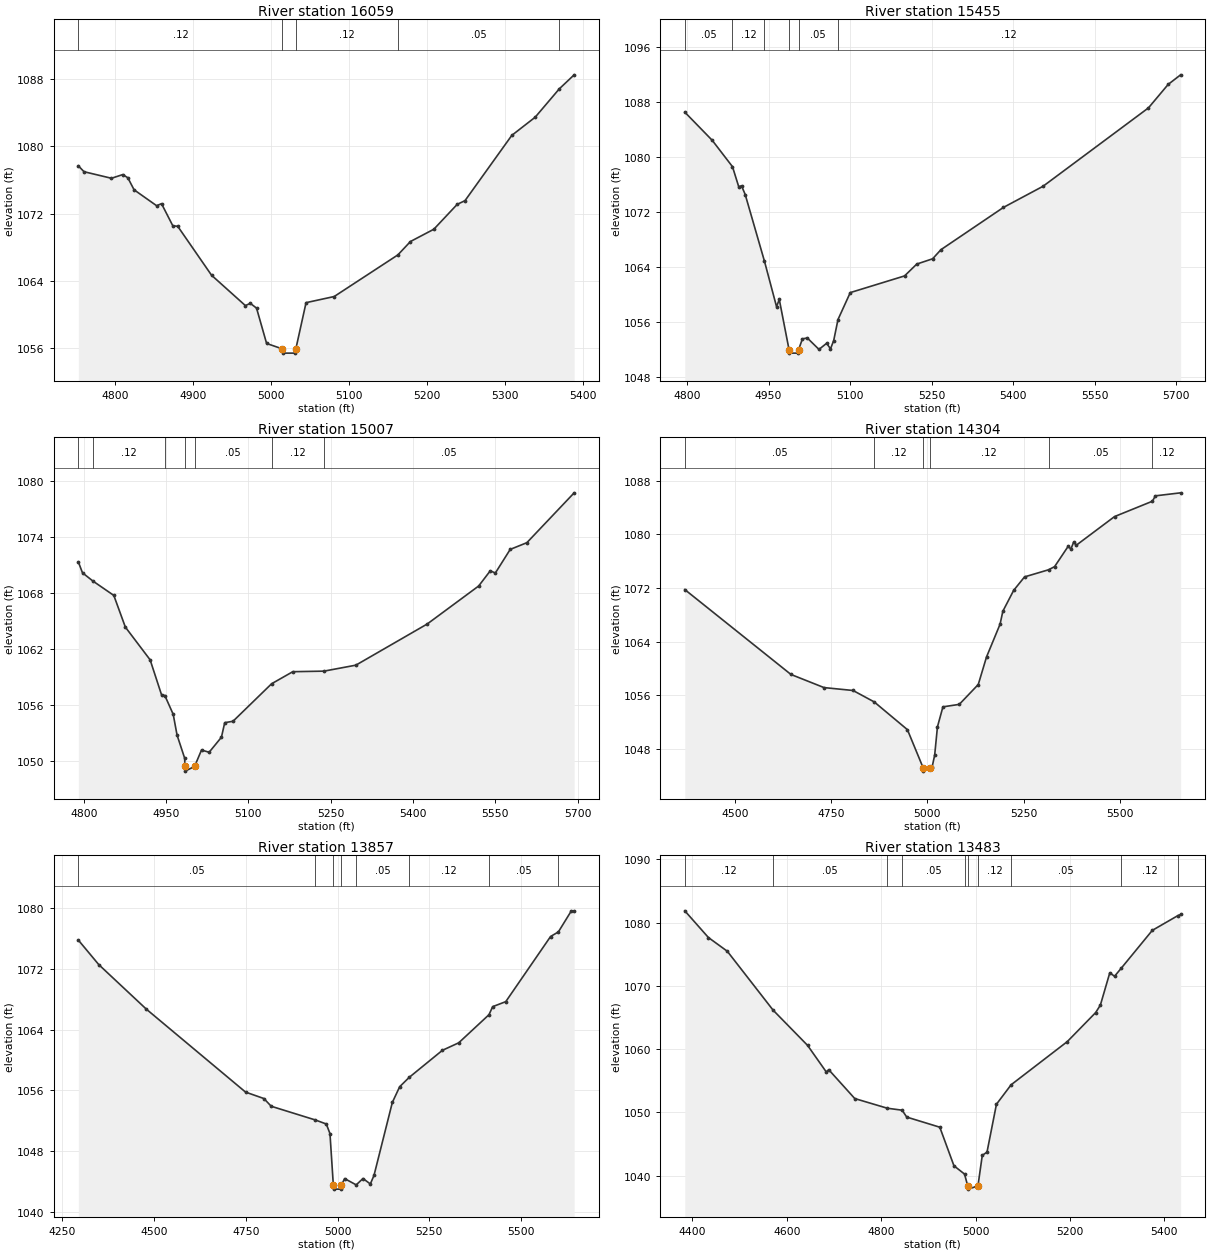
Type RM Length L Ch R = 1,16059,604,604,604
BEGIN DESCRIPTION:
BYRNES CREEK 26.0
END DESCRIPTION:
XS GIS Cut Line= 3
      2825505.66     10226703.10      2825824.21     10226952.51
      2826055.64     10226953.11
#Sta/Elev= 30
  4752.4 1077.70  4759.7 1077.00  4794.9 1076.22  4809.4 1076.66  4815.9 1076.28
  4823.9 1074.85  4852.8 1072.96  4859.1 1073.20  4873.6 1070.57  4879.9 1070.51
  4923.3 1064.69  4966.7 1061.08  4973.0 1061.35  4981.0 1060.78  4993.9 1056.58
  5014.2 1055.93  5014.7 1055.43  5030.9 1055.43  5031.4 1055.93  5044.5 1061.43
  5080.6 1062.16  5162.3 1067.11  5178.4 1068.70  5208.4 1070.16  5238.4 1073.12
  5248.4 1073.56  5308.4 1081.32  5338.4 1083.48  5369.4 1086.86  5388.4 1088.52
#Mann=5,-1,0
  4752.4    0.12       0  5014.2    0.07       0  5031.4    0.12       0
  5162.3    0.05       0  5369.4    0.12       0
Bank Sta=5014.2,5031.4
Exp/Cntr=0.3,0.1

Type RM Length L Ch R = 1,15455,448,448,448
BEGIN DESCRIPTION:
BYRNES CREEK 25.0
END DESCRIPTION:
XS GIS Cut Line= 3
      2825305.65     10227353.11      2825507.75     10227383.00
      2826105.68     10227003.12
#Sta/Elev= 30
  4795.7 1086.51  4846.3 1082.41  4883.5 1078.59  4895.0 1075.67  4900.1 1075.82
  4906.9 1074.55  4942.4 1064.85  4964.6 1058.26  4969.6 1059.32  4987.6 1052.02
  4988.1 1051.52  5004.7 1051.52  5005.2 1052.02  5012.2 1053.59  5021.2 1053.72
  5042.7 1052.06  5056.8 1052.95  5063.9 1052.14  5069.8 1053.35  5077.7 1056.40
  5100.3 1060.31  5200.2 1062.73  5222.7 1064.45  5251.9 1065.22  5267.2 1066.54
  5382.3 1072.68  5455.2 1075.75  5649.2 1087.13  5685.5 1090.54  5708.4 1091.93
#Mann=6,-1,0
  4795.7    0.05       0  4883.5    0.12       0  4942.4    0.05       0
  4987.6    0.05       0  5005.2    0.05       0  5077.7    0.12       0
Bank Sta=4987.6,5005.2
Exp/Cntr=0.3,0.1

Type RM Length L Ch R = 1,15007,703,703,703
BEGIN DESCRIPTION:
BYRNES CREEK 24.0
END DESCRIPTION:
XS GIS Cut Line= 3
      2825505.66     10227903.13      2825680.75     10227787.00
      2826055.68     10227203.11
#Sta/Elev= 30
  4789.9 1071.29  4797.5 1070.12  4816.5 1069.24  4854.6 1067.70  4875.6 1064.31
  4920.8 1060.80  4941.8 1057.02  4947.6 1056.98  4962.9 1054.96  4969.9 1052.74
  4983.9 1050.24  4984.1 1049.38  4984.6 1048.88  5001.8 1049.38  5014.5 1051.14
  5028.4 1050.90  5050.8 1052.51  5056.8 1054.07  5071.9 1054.22  5142.3 1058.24
  5180.9 1059.53  5237.7 1059.59  5295.9 1060.23  5426.0 1064.64  5519.8 1068.71
  5541.0 1070.34  5550.2 1070.10  5577.3 1072.63  5607.7 1073.35  5693.9 1078.69
#Mann=7,-1,0
  4789.9    0.05       0  4816.5    0.12       0  4947.6    0.05       0
  4984.1    0.05       0  5001.8    0.05       0  5142.3    0.12       0
  5237.7    0.05       0
Bank Sta=4984.1,5001.8
Exp/Cntr=0.3,0.1

Type RM Length L Ch R = 1,14304,447,447,447
BEGIN DESCRIPTION:
BYRNES CREEK 23.0
END DESCRIPTION:
XS GIS Cut Line= 3
      2825799.18     10228326.84      2826174.62     10228179.26
      2826784.46     10227539.04
#Sta/Elev= 30
  4370.0 1071.78  4645.6 1059.13  4731.6 1057.17  4806.9 1056.74  4861.8 1055.04
  4948.1 1050.90  4988.9 1045.22  4989.4 1044.72  5006.7 1045.22  5012.0 1045.27
  5018.9 1047.10  5026.1 1051.32  5040.3 1054.30  5082.8 1054.67  5132.1 1057.63
  5153.5 1061.73  5188.7 1066.62  5196.0 1068.56  5224.0 1071.66  5252.3 1073.67
  5314.6 1074.73  5330.3 1075.20  5365.5 1078.22  5372.7 1077.82  5379.7 1078.84
  5386.9 1078.40  5486.0 1082.66  5584.4 1084.95  5592.0 1085.75  5657.6 1086.20
#Mann=6,-1,0
  4370.0    0.05       0  4861.8    0.12       0  4988.9    0.07       0
  5006.7    0.12       0  5314.6    0.05       0  5584.4    0.12       0
Bank Sta=4988.9,5006.7
Exp/Cntr=0.3,0.1

Type RM Length L Ch R = 1,13857,374,374,374
BEGIN DESCRIPTION:
BYRNES CREEK 22.0
END DESCRIPTION:
XS GIS Cut Line= 3
      2825760.12     10228450.53      2826729.70     10228427.13
      2826948.26     10228739.75
#Sta/Elev= 30
  4293.4 1075.83  4349.0 1072.60  4479.0 1066.71  4749.1 1055.78  4799.1 1054.93
  4819.1 1053.91  4939.5 1052.10  4969.2 1051.57  4979.2 1050.31  4988.4 1043.48
  4988.9 1042.98  5009.5 1042.98  5010.0 1043.48  5019.2 1044.37  5050.7 1043.54
  5069.2 1044.38  5089.2 1043.66  5099.2 1044.79  5149.2 1054.42  5169.2 1056.49
  5195.1 1057.72  5285.6 1061.29  5330.1 1062.28  5412.6 1065.99  5422.6 1067.05
  5458.3 1067.71  5580.4 1076.30  5601.7 1076.91  5637.1 1079.69  5644.7 1079.66
#Mann=8,-1,0
  4293.4    0.05       0  4939.5    0.12       0  4988.4    0.07       0
  5010.0    0.12       0  5050.7    0.05       0  5195.1    0.12       0
  5412.6    0.05       0  5601.7    0.12       0
Bank Sta=4988.4,5010
Exp/Cntr=0.3,0.1

Type RM Length L Ch R = 1,13483,448,448,448
BEGIN DESCRIPTION:
BYRNES CREEK 21.0
END DESCRIPTION:
XS GIS Cut Line= 3
      2825905.68     10228803.11      2826521.50     10228793.00
      2826955.68     10228803.11
#Sta/Elev= 30
  4384.1 1081.88  4434.1 1077.66  4474.1 1075.49  4571.1 1066.18  4644.1 1060.61
  4683.9 1056.39  4688.9 1056.77  4744.1 1052.20  4813.1 1050.67  4844.4 1050.36
  4854.2 1049.27  4924.2 1047.67  4954.2 1041.57  4976.6 1040.26  4983.4 1038.38
  4983.9 1037.88  5005.0 1038.38  5014.2 1043.22  5024.2 1043.73  5044.2 1051.30
  5075.3 1054.38  5194.2 1061.20  5254.3 1065.79  5264.3 1066.97  5284.3 1072.09
  5294.3 1071.53  5309.0 1072.85  5374.3 1078.79  5428.6 1081.13  5434.3 1081.30
#Mann=10,-1,0
  4384.1    0.12       0  4571.1    0.05       0  4813.1    0.12       0
  4844.4    0.05       0  4976.6    0.12       0  4983.4    0.07       0
  5005.0    0.12       0  5075.3    0.05       0  5309.0    0.12       0
  5428.6    0.05       0
Bank Sta=4983.4,5005
Exp/Cntr=0.3,0.1

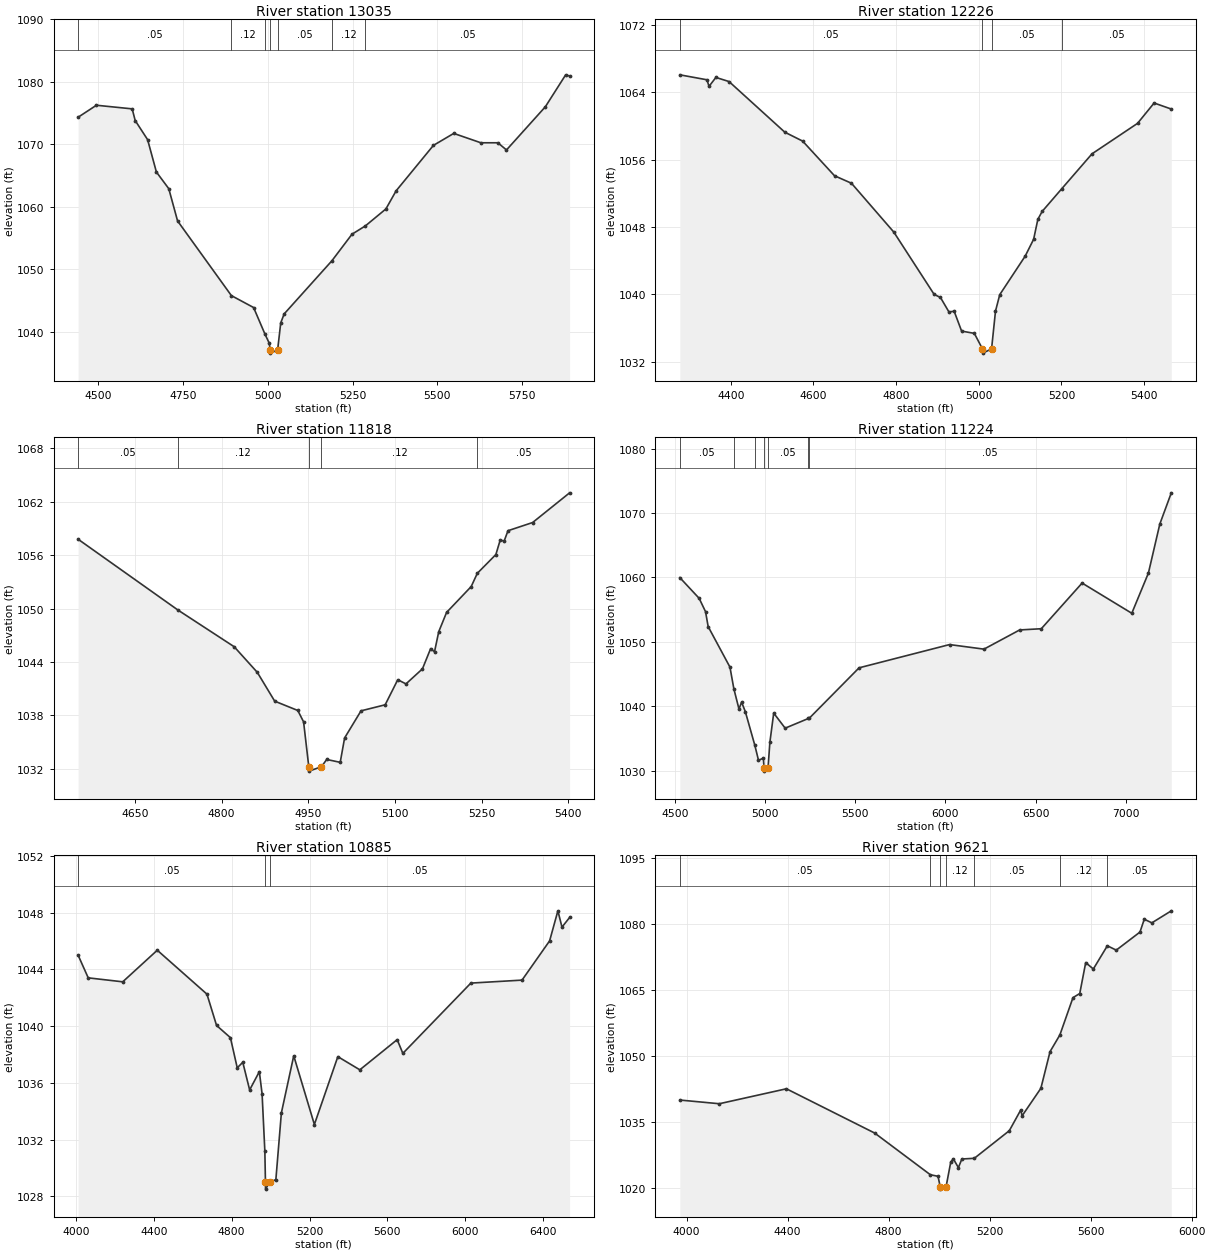
Type RM Length L Ch R = 1,13035,809,809,809
BEGIN DESCRIPTION:
BYRNES CREEK 20.0
END DESCRIPTION:
XS GIS Cut Line= 3
      2825944.94     10229142.13      2826234.42     10229241.80
      2827377.25     10229225.46
#Sta/Elev= 30
  4440.8 1074.33  4494.8 1076.25  4600.2 1075.67  4609.1 1073.80  4645.7 1070.74
  4671.6 1065.56  4708.1 1062.89  4734.0 1057.73  4892.7 1045.77  4958.2 1043.86
  4991.5 1039.63  5004.0 1038.19  5007.4 1037.06  5007.9 1036.56  5029.0 1037.06
  5038.2 1041.40  5048.3 1042.84  5189.1 1051.35  5248.3 1055.60  5288.0 1056.94
  5348.3 1059.65  5378.3 1062.54  5488.3 1069.82  5548.3 1071.74  5628.3 1070.24
  5678.3 1070.24  5703.8 1069.09  5818.3 1076.00  5878.3 1081.12  5889.9 1080.93
#Mann=7,-1,0
  4440.8    0.05       0  4892.7    0.12       0  4991.5    0.05       0
  5007.4    0.05       0  5029.0    0.05       0  5189.1    0.12       0
  5288.0    0.05       0
Bank Sta=5007.4,5029
Exp/Cntr=0.3,0.1

Type RM Length L Ch R = 1,12226,408,408,408
BEGIN DESCRIPTION:
BYRNES CREEK 19.0
END DESCRIPTION:
XS GIS Cut Line= 3
      2825960.53     10230173.38      2826841.03     10229975.08
      2827127.23     10229991.08
#Sta/Elev= 30
  4276.6 1066.10  4342.2 1065.51  4347.3 1064.73  4363.9 1065.79  4395.7 1065.30
  4530.6 1059.28  4573.8 1058.22  4650.9 1054.10  4691.9 1053.21  4794.4 1047.40
  4892.0 1039.99  4907.2 1039.63  4927.7 1037.91  4940.4 1037.99  4958.4 1035.63
  4989.2 1035.36  5008.9 1033.51  5009.4 1033.01  5030.9 1033.51  5040.4 1038.00
  5050.7 1039.96  5112.2 1044.54  5132.7 1046.55  5142.9 1048.92  5153.2 1049.85
  5200.8 1052.56  5274.0 1056.71  5384.1 1060.33  5424.2 1062.75  5465.8 1062.03
#Mann=4,-1,0
  4276.6    0.05       0  5008.9    0.03       0  5030.9    0.05       0
  5200.8    0.05       0
Bank Sta=5008.9,5030.9
Exp/Cntr=0.3,0.1

Type RM Length L Ch R = 1,11818,594,594,594
BEGIN DESCRIPTION:
BYRNES CREEK 18.0
END DESCRIPTION:
XS GIS Cut Line= 3
      2826255.73     10230403.11      2826703.75     10230419.00
      2827005.67     10230153.12
#Sta/Elev= 30
  4551.7 1057.79  4724.4 1049.83  4821.8 1045.70  4861.8 1042.82  4891.9 1039.58
  4931.9 1038.53  4941.9 1037.25  4950.9 1032.21  4951.4 1031.71  4972.9 1032.21
  4981.9 1033.02  5005.3 1032.70  5012.9 1035.44  5041.3 1038.49  5083.1 1039.17
  5104.9 1041.99  5119.1 1041.52  5147.6 1043.21  5161.8 1045.49  5168.5 1045.13
  5175.8 1047.39  5189.4 1049.56  5232.0 1052.47  5242.6 1053.96  5274.7 1056.07
  5282.3 1057.72  5288.9 1057.57  5295.7 1058.75  5338.3 1059.67  5402.3 1063.01
#Mann=5,-1,0
  4551.7    0.05       0  4724.4    0.12       0  4950.9    0.07       0
  4972.9    0.12       0  5242.6    0.05       0
Bank Sta=4950.9,4972.9
Exp/Cntr=0.3,0.1

Type RM Length L Ch R = 1,11224,339,339,339
BEGIN DESCRIPTION:
BYRNES CREEK 17.0
END DESCRIPTION:
XS GIS Cut Line= 3
      2826355.70     10231253.10      2826735.00     10230969.00
      2828305.70     10229353.09
#Sta/Elev= 30
  4526.1 1059.96  4633.4 1056.74  4668.8 1054.67  4683.4 1052.35  4804.3 1046.06
  4826.1 1042.68  4854.3 1039.56  4868.9 1040.62  4889.7 1039.14  4942.5 1033.91
  4962.6 1031.60  4989.7 1031.92  4993.6 1030.41  4994.1 1029.91  5015.7 1030.41
  5025.8 1034.37  5047.1 1038.92  5110.7 1036.58  5240.1 1038.09  5244.7 1038.13
  5520.9 1045.95  6023.0 1049.56  6213.9 1048.85  6412.0 1051.83  6532.1 1052.02
  6758.5 1059.11  7034.2 1054.42  7126.3 1060.65  7189.8 1068.28  7253.5 1073.12
#Mann=7,-1,0
  4526.1    0.05       0  4826.1    0.12       0  4942.5    0.05       0
  4993.6    0.03       0  5015.7    0.05       0  5240.1    0.12       0
  5244.7    0.05       0
Bank Sta=4993.6,5015.7
Exp/Cntr=0.3,0.1

Type RM Length L Ch R = 1,10885,1264,1264,1264
BEGIN DESCRIPTION:
Mapping XS 80f8400e
END DESCRIPTION:
XS GIS Cut Line= 5
      2826190.58     10232021.80      2826765.64     10231370.80
      2827188.82     10230925.92      2827568.59     10230426.79
      2827850.70     10230122.97
#Sta/Elev= 30
  4011.4 1045.01  4063.3 1043.41  4240.6 1043.13  4418.0 1045.36  4673.1 1042.26
  4722.5 1040.05  4793.6 1039.19  4828.7 1037.06  4857.2 1037.45  4892.4 1035.50
  4942.2 1036.79  4956.3 1035.23  4970.5 1031.18  4973.6 1029.00  4974.1 1028.50
  4995.7 1029.00  5027.1 1029.17  5055.4 1033.88  5118.9 1037.91  5224.9 1033.06
  5345.4 1037.85  5458.3 1036.92  5650.2 1039.05  5679.3 1038.08  6028.6 1043.04
  6291.4 1043.25  6433.1 1046.02  6475.6 1048.14  6496.6 1046.99  6535.8 1047.67
#Mann=3,-1,0
  4011.4    0.05       0  4973.6    0.05       0  4995.7    0.05       0
Bank Sta=4973.6,4995.7
Exp/Cntr=0.3,0.1

Type RM Length L Ch R = 1,9621,610,610,610
BEGIN DESCRIPTION:
Mapping XS 3ac1b4be
END DESCRIPTION:
XS GIS Cut Line= 3
      2826982.63     10231826.53      2827807.31     10231652.92
      2828901.92     10231512.03
#Sta/Elev= 30
  3973.0 1040.02  4129.4 1039.18  4395.1 1042.58  4744.8 1032.51  4965.2 1023.03
  4995.6 1022.68  5004.3 1020.26  5004.8 1019.76  5027.3 1020.26  5046.0 1025.93
  5056.1 1026.66  5076.3 1024.65  5089.9 1026.61  5139.3 1026.77  5277.9 1033.05
  5323.3 1037.77  5328.4 1036.42  5402.8 1042.68  5439.2 1051.03  5478.1 1054.82
  5530.0 1063.31  5556.8 1064.24  5580.4 1071.28  5610.6 1069.82  5666.1 1075.10
  5701.4 1074.11  5795.3 1078.22  5812.3 1081.13  5842.5 1080.32  5919.4 1083.05
#Mann=7,-1,0
  3973.0    0.05       0  4965.2    0.12       0  5004.3    0.07       0
  5027.3    0.12       0  5139.3    0.05       0  5478.1    0.12       0
  5666.1    0.05       0
Bank Sta=5004.3,5027.3
Exp/Cntr=0.3,0.1