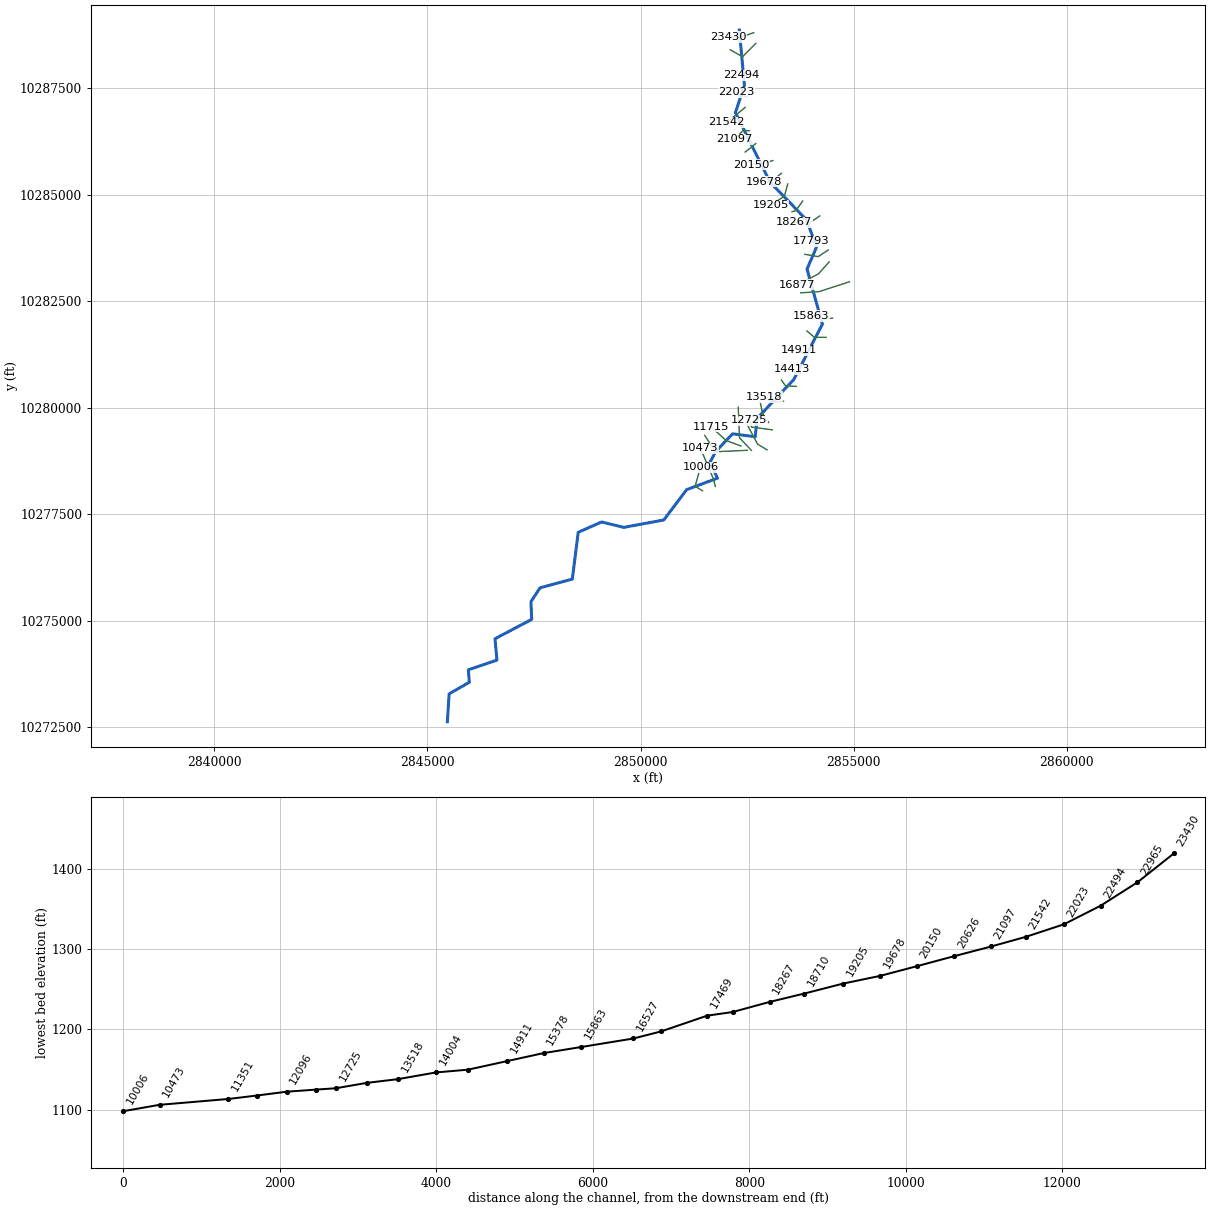
--- CEDAR HOLLOW CREEK.prj (project) ---

Proj Title=CEDAR HOLLOW CREEK Base Level Engineering
Current Plan=p01
Default Exp/Contr=0.3,0.1
English Units
Geom File=g01
Flow File=f01
Plan File=p01
Y Axis Title=Elevation
X Axis Title(PF)=Main Channel Distance
X Axis Title(XS)=Station
BEGIN DESCRIPTION:
CEDAR HOLLOW CREEK
END DESCRIPTION:
DSS Export Rating Curves= 0
DSS Export Rating Curve Sorted= 0
DSS Export Volume Flow Curves= 0
DXF OffsetX= 0
DXF OffsetY= 0
DXF ScaleX= 1
DXF ScaleY= 10

--- CEDAR HOLLOW CREEK.p01 (plan) ---

Plan Title=Multiple Run
Short Identifier=Multiple
Geom File=g01
Flow File=f01
Subcritical Flow
K Sum by GR= 0
Std Step Tol= 0.01
Critical Tol= 0.01
Num of Std Step Trials= 20
Max Error Tol= 0.3
Flow Tol Ratio= 0.001
Split Flow NTrial= 30
Split Flow Tol= 0.02
Split Flow Ratio= 0.02
Log Output Level= 0
Friction Slope Method= 1
Unsteady Friction Slope Method= 2
Unsteady Bridges Friction Slope Method= 1
Parabolic Critical Depth
Global Vel Dist=  1 , 1 , 1
Global Log Level= 0
CheckData=True
Encroach Param= -1, 0, 0, 0
BEGIN DESCRIPTION:
Multiple Run
END DESCRIPTION:

--- CEDAR HOLLOW CREEK.f01 (steady flow) ---

Flow Title=Multiple
Program Version=4.10
Number of Profiles= 7
Profile Names=10-year,25-year,50-year,1pct_min,100-year,1pct_plu,500-year
River Rch & RM=CEDAR HOLLOW CRE,Reach-1         ,23430
     427     686    1911    1695    2771    4530    4147
River Rch & RM=CEDAR HOLLOW CRE,Reach-1         ,16527
     713    1189    3069    2481    4488    8116    6650
River Rch & RM=CEDAR HOLLOW CRE,Reach-1         ,10473
     846    1431    3524    2737    5161    9733    7623
River Rch & RM=CEDAR HOLLOW CRE,Reach-1         ,7299
     952    1618    4146    3267    6106   11413    9004
River Rch & RM=CEDAR HOLLOW CRE,Reach-1         ,6847
    1139    1965    4786    3635    7056   13698   10356
River Rch & RM=CEDAR HOLLOW CRE,Reach-1         ,2480
    1392    2429    5965    4502    8840   17359   12920
Boundary for River Rch & Prof#=CEDAR HOLLOW CRE,Reach-1         , 1
Up Type= 0
Dn Type= 3
Dn Slope=0.005
Boundary for River Rch & Prof#=CEDAR HOLLOW CRE,Reach-1         , 2
Up Type= 0
Dn Type= 3
Dn Slope=0.005
Boundary for River Rch & Prof#=CEDAR HOLLOW CRE,Reach-1         , 3
Up Type= 0
Dn Type= 3
Dn Slope=0.005
Boundary for River Rch & Prof#=CEDAR HOLLOW CRE,Reach-1         , 4
Up Type= 0
Dn Type= 3
Dn Slope=0.005
Boundary for River Rch & Prof#=CEDAR HOLLOW CRE,Reach-1         , 5
Up Type= 0
Dn Type= 3
Dn Slope=0.005
Boundary for River Rch & Prof#=CEDAR HOLLOW CRE,Reach-1         , 6
Up Type= 0
Dn Type= 3
Dn Slope=0.005
Boundary for River Rch & Prof#=CEDAR HOLLOW CRE,Reach-1         , 7
Up Type= 0
Dn Type= 3
Dn Slope=0.005
DSS Import GetInterval= 0
DSS Import GetPeak= 0
DSS Import FillOption= 0

--- CEDAR HOLLOW CREEK.g01 (geometry) ---

Geom Title=Existing Conditions
Program Version=4.10

River Reach=CEDAR HOLLOW CRE,Reach-1
Reach XY= 30
       2852318.5       10288867.       2852438.5       10287568.
      2852227.25       10286931.       2853040.5       10285294.
        2853895.       10284412.       2854131.5       10283775.
       2853907.5       10283258.      2854267.25       10281963.
      2853597.25       10280665.        2852736.       10279750.
        2852691.       10279321.      2852161.25       10279390.
      2851760.25       10278969.        2851630.       10278719.
      2851807.25       10278349.        2851083.       10278080.
      2850545.75       10277368.        2849607.       10277194.
       2849087.5       10277321.        2848538.       10277079.
      2848399.75       10275980.        2847642.       10275776.
       2847428.5       10275450.       2847445.5       10275035.
      2846584.75       10274580.      2846630.25       10274079.
      2845959.75       10273852.        2845982.       10273559.
        2845508.       10273287.        2845467.       10272633.

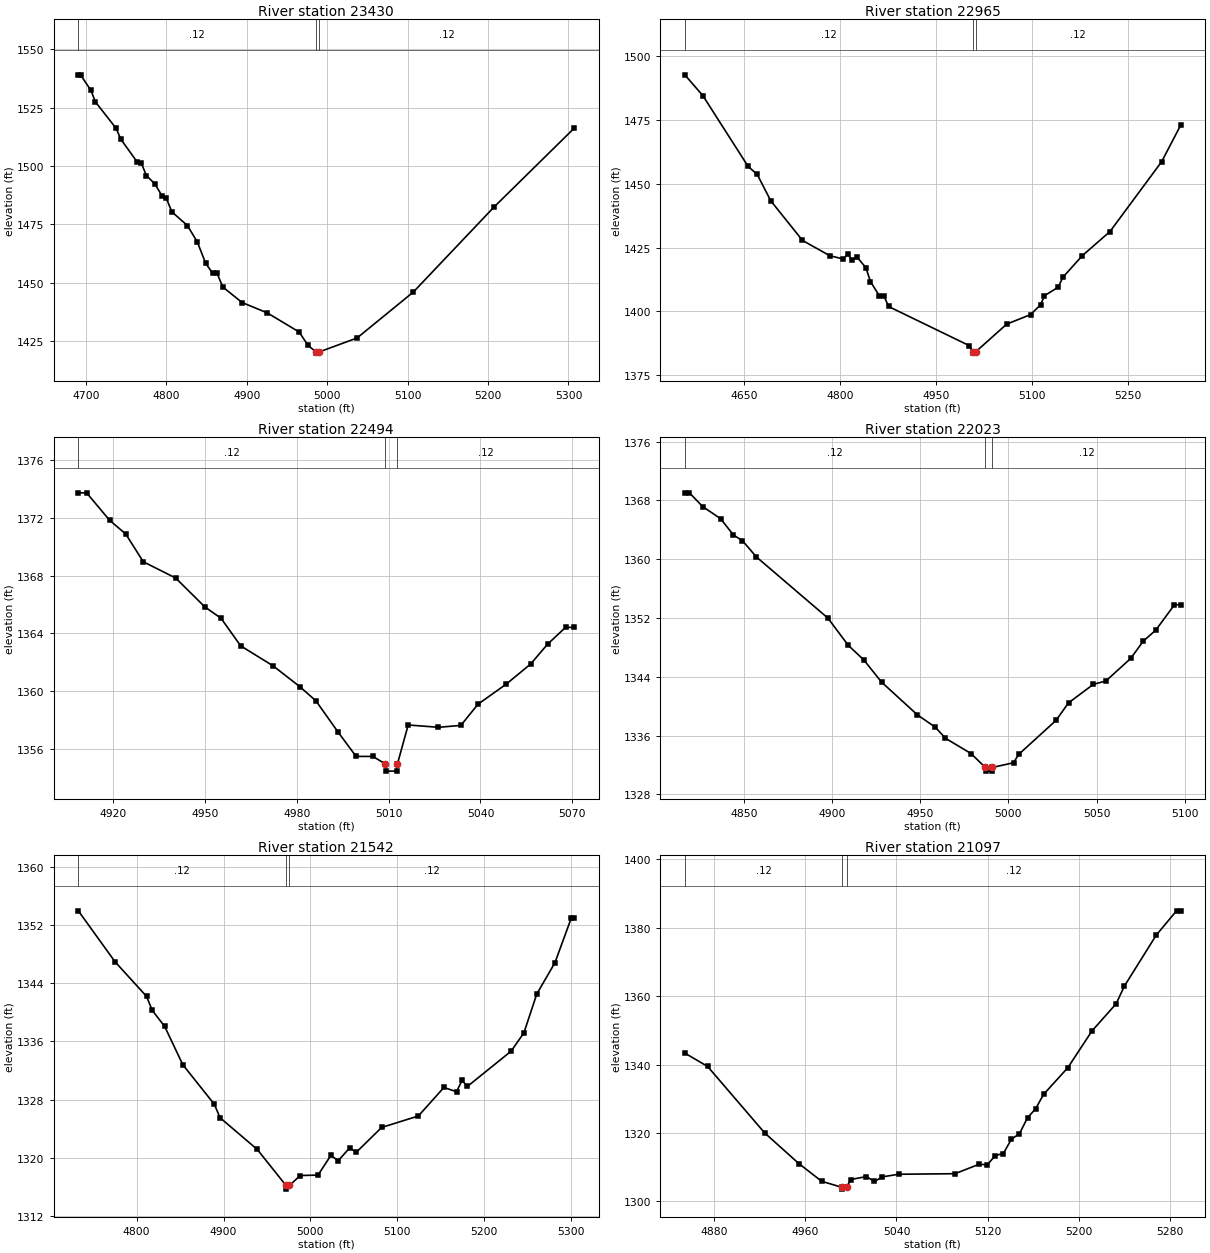
Type RM Length L Ch R = 1 ,23430   ,465,465,465
BEGIN DESCRIPTION:
CEDAR HOLLOW CREEK 50.0
END DESCRIPTION:
XS GIS Cut Line= 3
      2852655.71     10288803.12      2852362.75       10288703.
      2852055.65     10288703.11
#Sta/Elev= 30
  4690.4    1539  4693.1    1539  4706.1 1532.33  4711.6 1527.42  4737.4 1516.06
  4743.3 1511.38  4763.4 1501.77  4768.7 1501.26    4775 1495.85  4785.5 1492.32
  4794.7 1487.03    4800 1486.03  4806.7 1480.31  4826.1 1474.42  4838.4 1467.38
  4848.9 1458.17  4857.4 1454.06  4862.7 1454.19  4870.1  1448.1    4894 1441.46
  4925.3 1437.03  4965.2 1428.79  4975.8 1423.19  4985.9 1420.27  4986.2 1419.77
  4989.9 1420.27  5037.1 1426.26  5107.1 1445.95  5207.1 1482.24  5307.1 1516.12
#Mann= 3 ,-1 , 0
  4690.4     .12       0  4985.9     .07       0  4989.9     .12       0
Bank Sta=4985.9,4989.9
XS Rating Curve= 0 ,0
Exp/Cntr=0.3,0.1

Type RM Length L Ch R = 1 ,22965   ,471,471,471
BEGIN DESCRIPTION:
CEDAR HOLLOW CREEK 49.0
END DESCRIPTION:
XS GIS Cut Line= 3
      2852705.66     10288553.09      2852394.25       10288239.
      2852105.66     10288403.13
#Sta/Elev= 30
  4557.7  1492.5  4585.9 1484.36  4656.6 1456.69  4670.8 1453.56    4692 1443.24
  4741.5 1427.77  4783.9 1421.83  4805.2  1420.5  4812.2  1422.4  4819.3 1419.94
  4826.3 1421.33  4840.5 1417.14  4847.6 1411.71  4861.7 1406.04  4868.8 1405.98
  4875.9 1401.95  5002.1 1386.63  5007.9 1384.22  5008.1 1383.72  5011.9 1384.22
  5060.3 1395.04  5097.7 1398.79  5113.4 1402.66  5119.4 1406.18    5141 1409.51
  5147.9 1413.31  5178.5 1421.82  5221.7 1431.25  5302.4 1458.57    5332 1472.78
#Mann= 3 ,-1 , 0
  4557.7     .12       0  5007.9     .07       0  5011.9     .12       0
Bank Sta=5007.9,5011.9
XS Rating Curve= 0 ,0
Exp/Cntr=0.3,0.1

Type RM Length L Ch R = 1 ,22494   ,471,471,471
BEGIN DESCRIPTION:
CEDAR HOLLOW CREEK 48.0
END DESCRIPTION:
XS GIS Cut Line= 3
      2852505.69     10287803.11       2852419.5       10287773.
      2852355.65     10287803.13
#Sta/Elev= 28
  4908.7 1373.74  4911.4 1373.74  4918.9 1371.84  4924.2 1370.88  4929.9 1368.96
  4940.5 1367.83    4950 1365.83  4955.3 1365.04  4961.7 1363.13  4972.3 1361.74
    4981  1360.3  4986.3 1359.31  4993.4 1357.18  4999.4 1355.46  5004.9 1355.46
  5008.9 1354.94  5009.1 1354.44  5012.6 1354.44  5012.9 1354.94  5016.4 1357.64
  5026.3 1357.48  5033.6 1357.61  5039.2 1359.08  5048.4 1360.47  5056.4 1361.87
  5061.9 1363.24  5067.8 1364.41  5070.6 1364.41
#Mann= 3 ,-1 , 0
  4908.7     .12       0  5008.9     .07       0  5012.9     .12       0
Bank Sta=5008.9,5012.9
XS Rating Curve= 0 ,0
Exp/Cntr=0.3,0.1

Type RM Length L Ch R = 1 ,22023   ,481,481,481
BEGIN DESCRIPTION:
CEDAR HOLLOW CREEK 47.0
END DESCRIPTION:
XS GIS Cut Line= 3
      2852505.73      10287303.1      2852324.75       10287334.
      2852255.69     10287403.11
#Sta/Elev= 30
  4816.4 1369.04    4819 1369.04  4826.6 1367.16  4836.7 1365.52    4844  1363.3
  4849.1 1362.53    4857 1360.32  4897.6 1351.99  4909.2 1348.27  4917.9 1346.32
    4928 1343.29  4948.3 1338.84  4958.5 1337.15  4964.3 1335.64  4978.8 1333.56
  4986.9 1331.67  4987.2 1331.17  4990.7 1331.17  4990.9 1331.67  5002.9 1332.31
  5005.8 1333.44    5027 1338.07  5034.1 1340.46  5048.2 1342.98  5055.3 1343.44
  5069.4 1346.51  5076.5 1348.86  5083.6 1350.35  5094.2 1353.81  5097.7 1353.81
#Mann= 3 ,-1 , 0
  4816.4     .12       0  4986.9     .07       0  4990.9     .12       0
Bank Sta=4986.9,4990.9
XS Rating Curve= 0 ,0
Exp/Cntr=0.3,0.1

Type RM Length L Ch R = 1 ,21542   ,445,445,445
BEGIN DESCRIPTION:
CEDAR HOLLOW CREEK 46.0
END DESCRIPTION:
XS GIS Cut Line= 3
      2852455.67      10287053.1      2852252.25       10286880.
      2852005.65     10286703.08
#Sta/Elev= 30
  4732.9 1353.96  4775.1 1346.96  4811.4 1342.19    4818 1340.26  4832.3 1338.05
  4853.1  1332.8  4889.4 1327.35    4896  1325.5  4938.8 1321.14  4971.9 1316.18
  4972.2 1315.68  4975.9 1316.18  4988.2 1317.55  5008.7 1317.61  5023.5 1320.31
    5032  1319.6    5045 1321.33  5052.9 1320.76  5081.9 1324.16  5124.2 1325.74
  5153.6 1329.66  5168.1 1329.08  5174.5 1330.63  5180.7 1329.81    5231 1334.66
  5245.7 1337.19  5260.5 1342.52  5281.4 1346.83  5300.4 1353.03  5303.5 1353.03
#Mann= 3 ,-1 , 0
  4732.9     .12       0  4971.9     .07       0  4975.9     .12       0
Bank Sta=4971.9,4975.9
XS Rating Curve= 0 ,0
Exp/Cntr=0.3,0.1

Type RM Length L Ch R = 1 ,21097   ,471,471,471
BEGIN DESCRIPTION:
CEDAR HOLLOW CREEK 45.0
END DESCRIPTION:
XS GIS Cut Line= 3
      2852555.72     10286503.11        2852410.       10286508.
      2852205.65     10286303.08
#Sta/Elev= 30
  4854.2 1343.34  4874.2 1339.45  4924.3 1320.01  4954.3 1311.04  4974.3 1305.87
  4992.3 1304.07  4992.6 1303.57  4996.3 1304.07  4999.7 1306.37  5013.6 1307.24
  5020.7 1305.81  5027.7 1307.16  5041.9 1307.92  5091.4 1308.08  5112.6 1310.86
  5119.7 1310.66  5126.7  1313.4  5133.8 1313.98  5140.9 1318.18  5147.9 1319.75
    5155 1324.44  5162.1 1327.05  5169.1 1331.27  5190.4 1339.08  5211.6 1349.82
  5232.8 1357.77  5239.9 1362.86  5268.1 1377.88  5285.8 1384.94  5289.4 1384.94
#Mann= 3 ,-1 , 0
  4854.2     .12       0  4992.3     .07       0  4996.3     .12       0
Bank Sta=4992.3,4996.3
XS Rating Curve= 0 ,0
Exp/Cntr=0.3,0.1

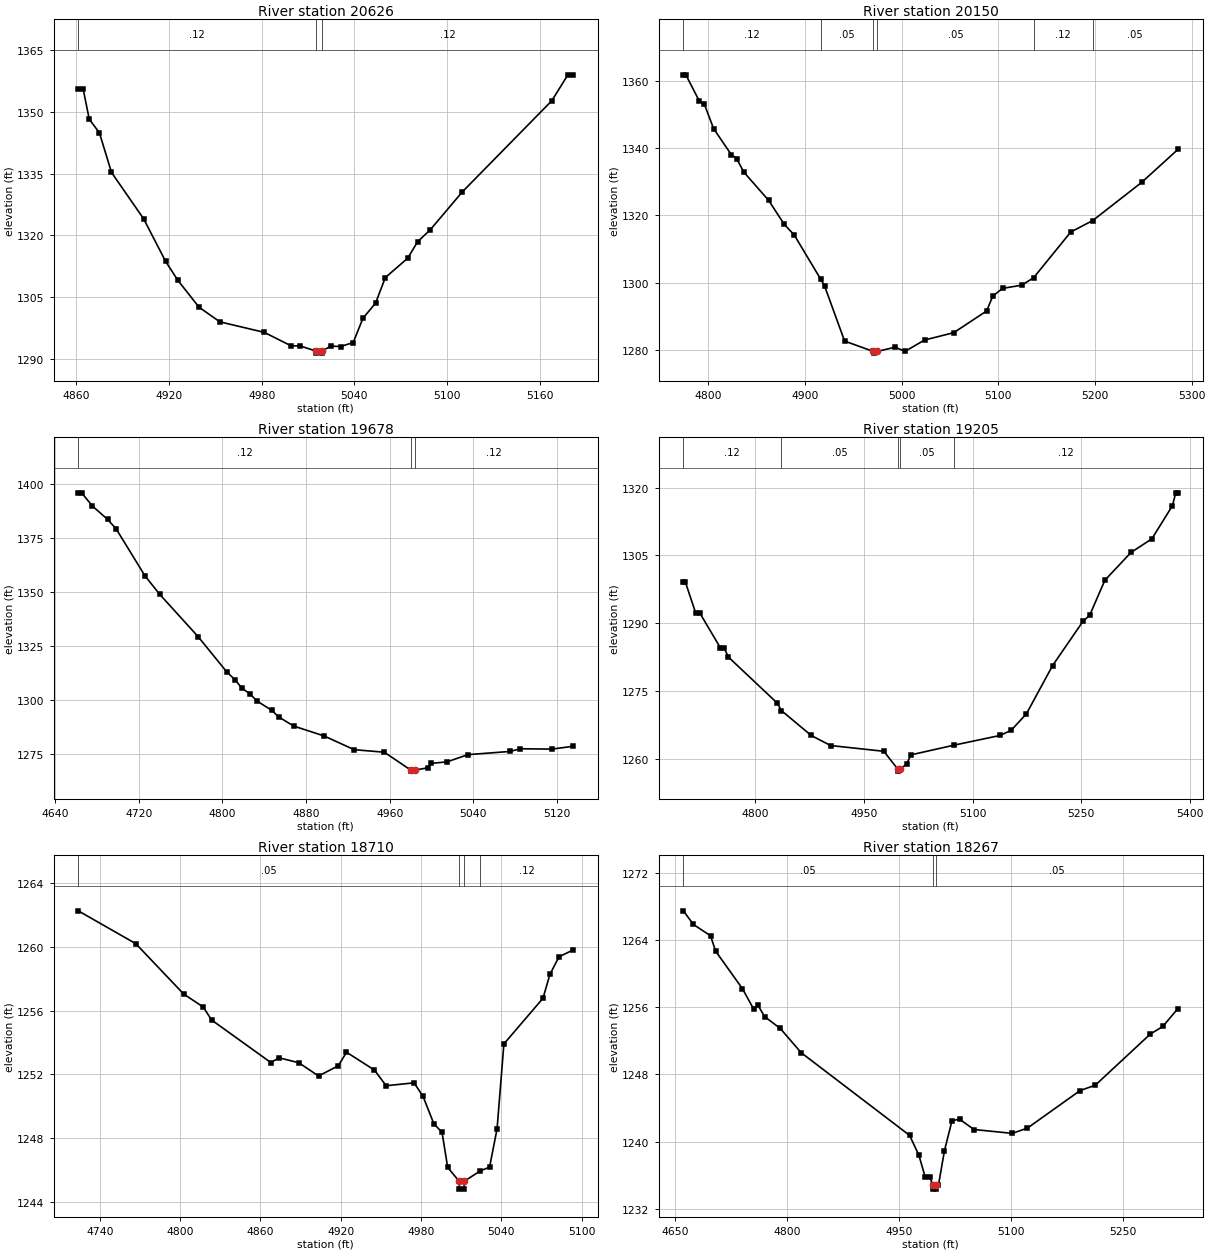
Type RM Length L Ch R = 1 ,20626   ,476,476,476
BEGIN DESCRIPTION:
CEDAR HOLLOW CREEK 44.0
END DESCRIPTION:
XS GIS Cut Line= 3
      2852705.67      10286203.1      2852599.25       10286114.
      2852455.69     10286003.11
#Sta/Elev= 30
  4861.2 1355.39  4864.4 1355.39  4868.3 1348.17  4874.9 1344.85  4882.7 1335.28
  4903.5 1324.05  4917.8 1313.71  4925.6 1309.19  4939.4 1302.63  4952.9 1299.09
  4981.6 1296.55  4999.1 1293.27  5004.8 1293.27  5015.1 1292.02  5015.4 1291.52
  5018.9 1291.52  5019.1 1292.02  5024.7 1293.23    5031 1293.12  5039.2 1294.08
  5045.5 1299.95  5053.7 1303.64    5060 1309.81  5074.5 1314.51  5080.9 1318.49
    5089 1321.34  5109.8 1330.54  5167.8 1352.63  5178.2  1358.9  5181.4  1358.9
#Mann= 3 ,-1 , 0
  4861.2     .12       0  5015.1     .07       0  5019.1     .12       0
Bank Sta=5015.1,5019.1
XS Rating Curve= 0 ,0
Exp/Cntr=0.3,0.1

Type RM Length L Ch R = 1 ,20150   ,472,472,472
BEGIN DESCRIPTION:
CEDAR HOLLOW CREEK 43.0
END DESCRIPTION:
XS GIS Cut Line= 3
      2853105.66      10285803.1      2852889.25       10285739.
      2852605.71     10285703.12
#Sta/Elev= 30
  4774.3 1361.83  4776.9 1361.83  4790.9 1353.98  4796.1 1353.05  4805.6 1345.82
  4824.1 1338.01  4829.4 1336.93  4836.8  1332.9  4862.6 1324.45  4878.6 1317.37
    4889 1314.17  4916.2  1301.1  4920.3 1299.06  4941.1  1282.6  4970.8 1279.52
    4971 1279.02  4974.8 1279.52  4993.3 1280.79  5003.5 1279.54  5023.8 1282.92
    5054 1285.11    5088 1291.57  5094.3 1295.98  5104.4 1298.28  5124.6 1299.26
  5136.7  1301.5    5175 1315.06  5197.7 1318.47  5248.3 1329.82  5285.8 1339.62
#Mann= 6 ,-1 , 0
  4774.3     .12       0  4916.2     .05       0  4970.8     .05       0
  4974.8     .05       0  5136.7     .12       0  5197.7     .05       0
Bank Sta=4970.8,4974.8
XS Rating Curve= 0 ,0
Exp/Cntr=0.3,0.1

Type RM Length L Ch R = 1 ,19678   ,473,473,473
BEGIN DESCRIPTION:
CEDAR HOLLOW CREEK 42.0
END DESCRIPTION:
XS GIS Cut Line= 3
      2853305.67      10285503.1       2853040.5       10285294.
      2852905.71     10285303.11
#Sta/Elev= 30
  4662.3 1395.93  4665.5 1395.93  4675.9 1389.77  4690.3 1383.61  4698.4  1379.3
    4726 1357.47    4740 1348.93  4776.9  1329.2  4804.2  1312.9  4812.2 1309.21
  4818.6 1305.39  4826.7 1302.58    4833 1299.41  4847.5 1294.97  4853.8    1292
  4868.3 1287.73  4897.2 1283.18  4926.1 1276.78  4954.9 1275.61  4980.1 1267.34
  4980.4 1266.84  4984.1 1267.34  4996.6 1268.38  4999.9 1270.45  5014.8 1271.14
  5034.9 1274.49    5075 1275.97    5085 1277.21  5115.1 1277.05  5135.1 1278.35
#Mann= 3 ,-1 , 0
  4662.3     .12       0  4980.1     .07       0  4984.1     .12       0
Bank Sta=4980.1,4984.1
XS Rating Curve= 0 ,0
Exp/Cntr=0.3,0.1

Type RM Length L Ch R = 1 ,19205   ,495,495,495
BEGIN DESCRIPTION:
CEDAR HOLLOW CREEK 41.0
END DESCRIPTION:
XS GIS Cut Line= 3
      2853455.69     10285253.12        2853375.       10284965.
       2853055.7     10284753.12
#Sta/Elev= 30
  4700.8 1299.18  4703.4 1299.18  4717.9 1292.22  4723.1 1292.35    4752 1284.52
  4757.2 1284.42  4763.1 1282.47  4830.6 1272.26  4836.1 1270.64  4877.3 1265.12
    4904  1262.9  4977.5 1261.62  4996.4 1257.73  4996.6 1257.23  5000.4 1257.73
  5008.8 1258.78  5014.8 1260.83  5074.3 1262.98  5138.1 1265.14  5153.2 1266.28
  5174.2 1269.92  5210.3 1280.61  5252.4 1290.44  5261.4 1291.72  5282.5 1299.52
  5318.6 1305.67  5347.2 1308.66  5375.7 1316.02  5380.2 1318.86  5383.2 1318.86
#Mann= 5 ,-1 , 0
  4700.8     .12       0  4836.1     .05       0  4996.4     .03       0
  5000.4     .05       0  5074.3     .12       0
Bank Sta=4996.4,5000.4
XS Rating Curve= 0 ,0
Exp/Cntr=0.3,0.1

Type RM Length L Ch R = 1 ,18710   ,443,443,443
BEGIN DESCRIPTION:
CEDAR HOLLOW CREEK 40.0
END DESCRIPTION:
XS GIS Cut Line= 3
      2853805.66     10284853.08      2853645.75       10284628.
      2853555.72     10284603.12
#Sta/Elev= 30
  4723.9 1262.25  4766.9 1260.19  4802.6 1257.04  4817.3 1256.22  4823.5 1255.41
  4867.8 1252.74  4873.9 1253.04  4888.7 1252.73  4903.4  1251.9  4918.2 1252.54
  4924.3 1253.39  4945.2 1252.27  4953.9 1251.29  4974.8 1251.47  4981.5 1250.62
  4989.5 1248.92  4995.7 1248.36  4999.9 1246.17  5008.4 1245.31  5008.7 1244.81
  5012.2 1244.81  5012.4 1245.31  5024.2 1245.95  5031.2 1246.19  5036.8 1248.59
  5041.9 1253.91  5071.1 1256.77  5076.3 1258.27  5083.1 1259.37  5093.4 1259.79
#Mann= 4 ,-1 , 0
  4723.9     .05       0  5008.4     .05       0  5012.4     .05       0
  5024.2     .12       0
Bank Sta=5008.4,5012.4
XS Rating Curve= 0 ,0
Exp/Cntr=0.3,0.1

Type RM Length L Ch R = 1 ,18267   ,474,474,474
BEGIN DESCRIPTION:
CEDAR HOLLOW CREEK 39.0
END DESCRIPTION:
XS GIS Cut Line= 3
      2854205.69     10284503.11       2853926.5       10284311.
      2853605.65     10284353.12
#Sta/Elev= 30
  4661.1 1267.48  4674.6 1265.86  4697.5 1264.51  4704.4 1262.67  4740.2 1258.22
  4755.1 1255.81  4761.2 1256.21    4770 1254.88    4791 1253.47  4818.9 1250.59
  4964.2 1240.74  4976.7 1238.36  4985.1 1235.77  4991.2 1235.75  4995.5 1234.84
  4995.7 1234.34  4999.2 1234.34  4999.5 1234.84  5002.9 1234.84  5010.9 1238.93
    5021 1242.49  5031.1 1242.67  5050.4 1241.44  5101.7 1240.98  5121.9  1241.6
  5192.5 1246.07    5213 1246.72  5286.7 1252.81  5303.4 1253.71  5323.6 1255.84
#Mann= 3 ,-1 , 0
  4661.1     .05       0  4995.5     .03       0  4999.5     .05       0
Bank Sta=4995.5,4999.5
XS Rating Curve= 0 ,0
Exp/Cntr=0.3,0.1

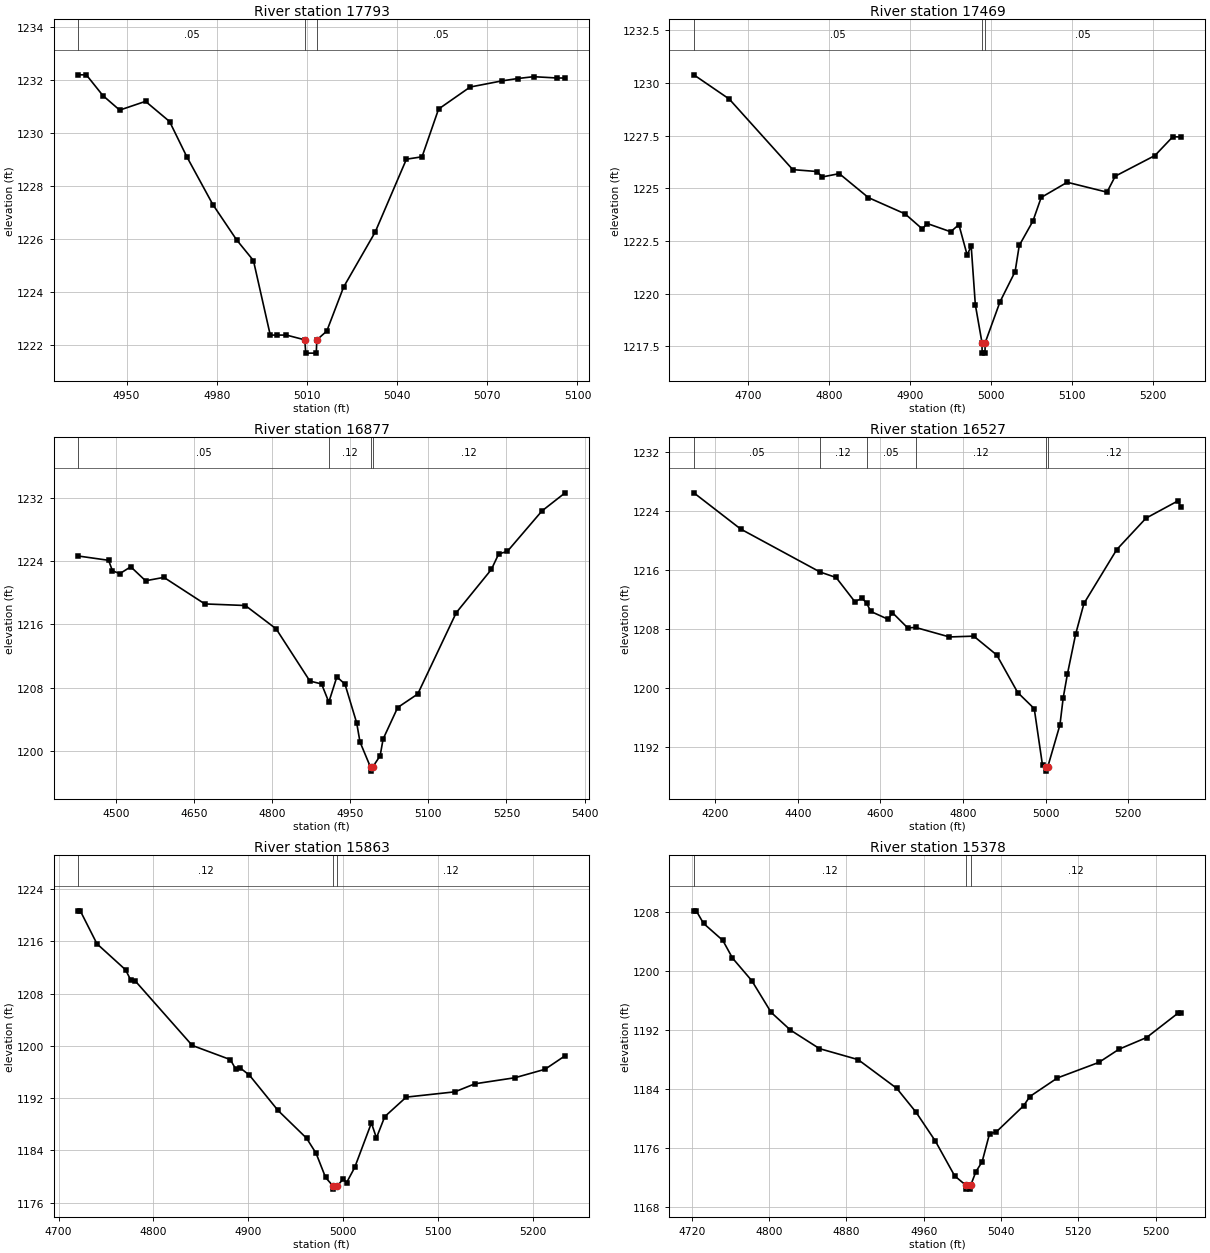
Type RM Length L Ch R = 1 ,17793   ,324,324,324
BEGIN DESCRIPTION:
CEDAR HOLLOW CREEK 38.0
END DESCRIPTION:
XS GIS Cut Line= 3
       2854155.7     10283903.12      2854096.75       10283873.
       2854005.7     10283903.11
#Sta/Elev= 29
  4933.8 1232.19  4936.6 1232.19  4942.1 1231.41  4947.7 1230.86  4956.3 1231.19
  4964.3 1230.43    4970 1229.11  4978.7  1227.3  4986.6 1225.97  4992.2 1225.19
  4997.8 1222.38    5000 1222.38  5003.2 1222.38  5009.3  1222.2  5009.6  1221.7
  5013.1  1221.7  5013.3  1222.2  5016.6 1222.53  5022.2 1224.19  5032.7 1226.26
  5043.1 1229.01  5048.3  1229.1  5053.8  1230.9  5064.3 1231.73  5074.8 1231.96
  5080.1 1232.05  5085.4 1232.12  5093.3 1232.07  5095.9 1232.07
#Mann= 3 ,-1 , 0
  4933.8     .05       0  5009.3     .05       0  5013.3     .05       0
Bank Sta=5009.3,5013.3
XS Rating Curve= 0 ,0
Exp/Cntr=0.3,0.1

Type RM Length L Ch R = 1 ,17469   ,592,592,592
BEGIN DESCRIPTION:
CEDAR HOLLOW CREEK 37.0
END DESCRIPTION:
XS GIS Cut Line= 3
      2854405.71     10283703.13      2854169.11     10283547.81
      2853855.68     10283603.11
#Sta/Elev= 30
    4633 1230.38  4676.7 1229.23  4755.1 1225.88  4785.2 1225.79  4791.2 1225.53
  4812.5 1225.69  4848.5 1224.55  4893.7 1223.78  4914.8 1223.07  4921.2 1223.32
    4950 1222.93  4960.1 1223.27  4970.3 1221.83  4975.3 1222.25  4980.4 1219.47
  4988.6 1217.67  4988.8 1217.17  4992.3 1217.17  4992.6 1217.67  5010.9 1219.61
  5029.5 1221.04  5034.6 1222.28  5051.5 1223.44  5061.7 1224.56  5093.8 1225.28
  5142.9 1224.81  5153.1 1225.57  5202.1 1226.55  5224.1 1227.44  5234.3 1227.43
#Mann= 3 ,-1 , 0
    4633     .05       0  4988.6     .03       0  4992.6     .05       0
Bank Sta=4988.6,4992.6
XS Rating Curve= 0 ,0
Exp/Cntr=0.3,0.1

Type RM Length L Ch R = 1 ,16877   ,350,350,350
BEGIN DESCRIPTION:
CEDAR HOLLOW CREEK 36.0
END DESCRIPTION:
XS GIS Cut Line= 3
      2854427.19     10283425.06        2854176.     10283143.28
      2853679.71     10282888.61
#Sta/Elev= 30
  4427.4 1224.66  4486.3 1224.11  4493.8 1222.77    4508 1222.43  4528.9 1223.29
  4557.3 1221.52  4592.5 1221.95    4671 1218.59  4748.8 1218.39  4807.9 1215.44
  4872.7 1208.83  4895.2 1208.46  4909.1 1206.16  4924.5 1209.36  4940.1 1208.44
  4962.6 1203.53  4968.9 1201.13  4989.1 1197.93  4989.3 1197.43  4993.1 1197.93
  5007.6 1199.37  5013.3 1201.49  5041.3 1205.48  5079.8 1207.19  5153.7 1217.48
  5221.1 1222.95  5235.2 1224.92  5251.7 1225.23  5318.3 1230.36  5362.7 1232.65
#Mann= 4 ,-1 , 0
  4427.4     .05       0  4909.1     .12       0  4989.1     .07       0
  4993.1     .12       0
Bank Sta=4989.1,4993.1
XS Rating Curve= 0 ,0
Exp/Cntr=0.3,0.1

Type RM Length L Ch R = 1 ,16527   ,664,664,664
BEGIN DESCRIPTION:
CEDAR HOLLOW CREEK 35.0
END DESCRIPTION:
XS GIS Cut Line= 3
      2854903.44     10282957.63      2854193.24     10282727.57
      2853761.01     10282697.67
#Sta/Elev= 30
  4148.3 1226.44  4261.6 1221.53    4454 1215.69  4492.8 1214.95  4538.1 1211.67
  4555.9 1212.13  4566.5 1211.48  4576.9 1210.34    4619 1209.27  4628.9 1210.19
  4666.1 1208.11  4685.2 1208.17  4767.3 1206.88  4826.1 1206.99  4881.8 1204.43
  4932.5 1199.34  4972.6 1197.15  4992.6 1189.46  5000.4 1189.17  5000.7 1188.67
  5004.9 1189.17  5034.8 1194.94  5042.7 1198.61  5052.8 1201.81  5072.8 1207.25
  5092.9 1211.42  5172.4 1218.74  5243.2    1223  5320.1 1225.33  5328.1 1224.53
#Mann= 6 ,-1 , 0
  4148.3     .05       0    4454     .12       0  4566.5     .05       0
  4685.2     .12       0  5000.4     .07       0  5004.9     .12       0
Bank Sta=5000.4,5004.9
XS Rating Curve= 0 ,0
Exp/Cntr=0.3,0.1

Type RM Length L Ch R = 1 ,15863   ,485,485,485
BEGIN DESCRIPTION:
CEDAR HOLLOW CREEK 34.0
END DESCRIPTION:
XS GIS Cut Line= 3
      2854505.72     10282103.11      2854227.25       10282078.
      2854005.64     10282153.13
#Sta/Elev= 30
  4720.4 1220.67  4722.9 1220.67  4740.5 1215.62  4770.6 1211.65  4775.9 1210.14
  4780.9 1209.93  4840.9 1200.07  4881.1  1197.9  4886.8 1196.44  4891.8 1196.59
  4901.2 1195.52  4931.3 1190.13  4961.4 1185.88  4971.5 1183.56  4981.5 1179.86
  4989.2 1178.58  4989.5 1178.08  4993.9 1178.58    5000 1179.63  5003.6 1179.06
  5012.2  1181.4  5029.8  1188.2  5035.1 1185.92  5043.9 1189.18  5066.5 1192.16
  5117.8 1192.97  5138.9  1194.2  5181.2 1195.13  5212.8 1196.42    5234 1198.49
#Mann= 3 ,-1 , 0
  4720.4     .12       0  4989.2     .07       0  4993.9     .12       0
Bank Sta=4989.2,4993.9
XS Rating Curve= 0 ,0
Exp/Cntr=0.3,0.1

Type RM Length L Ch R = 1 ,15378   ,467,467,467
BEGIN DESCRIPTION:
CEDAR HOLLOW CREEK 33.0
END DESCRIPTION:
XS GIS Cut Line= 3
      2854355.63     10281653.11      2854077.75       10281656.
      2853905.67     10281803.12
#Sta/Elev= 30
  4722.1 1208.13  4724.6 1208.13  4732.1 1206.43  4752.1 1204.12  4762.1 1201.73
  4782.1 1198.66  4802.1 1194.37  4822.1 1191.97  4852.1 1189.46  4892.1 1187.97
  4932.1 1184.08  4952.1 1180.84  4972.1 1176.93  4992.1 1172.21  5003.9 1170.92
  5004.3 1170.42  5008.3 1170.42  5008.6 1170.92    5014 1172.77  5020.5 1174.13
  5028.2 1177.95  5034.8 1178.13  5063.4 1181.71  5069.9 1182.97  5098.5 1185.49
  5141.3 1187.59  5162.2 1189.38  5190.7 1190.96  5223.1 1194.25  5226.4 1194.25
#Mann= 3 ,-1 , 0
  4722.1     .12       0  5003.9     .07       0  5008.6     .12       0
Bank Sta=5003.9,5008.6
XS Rating Curve= 0 ,0
Exp/Cntr=0.3,0.1

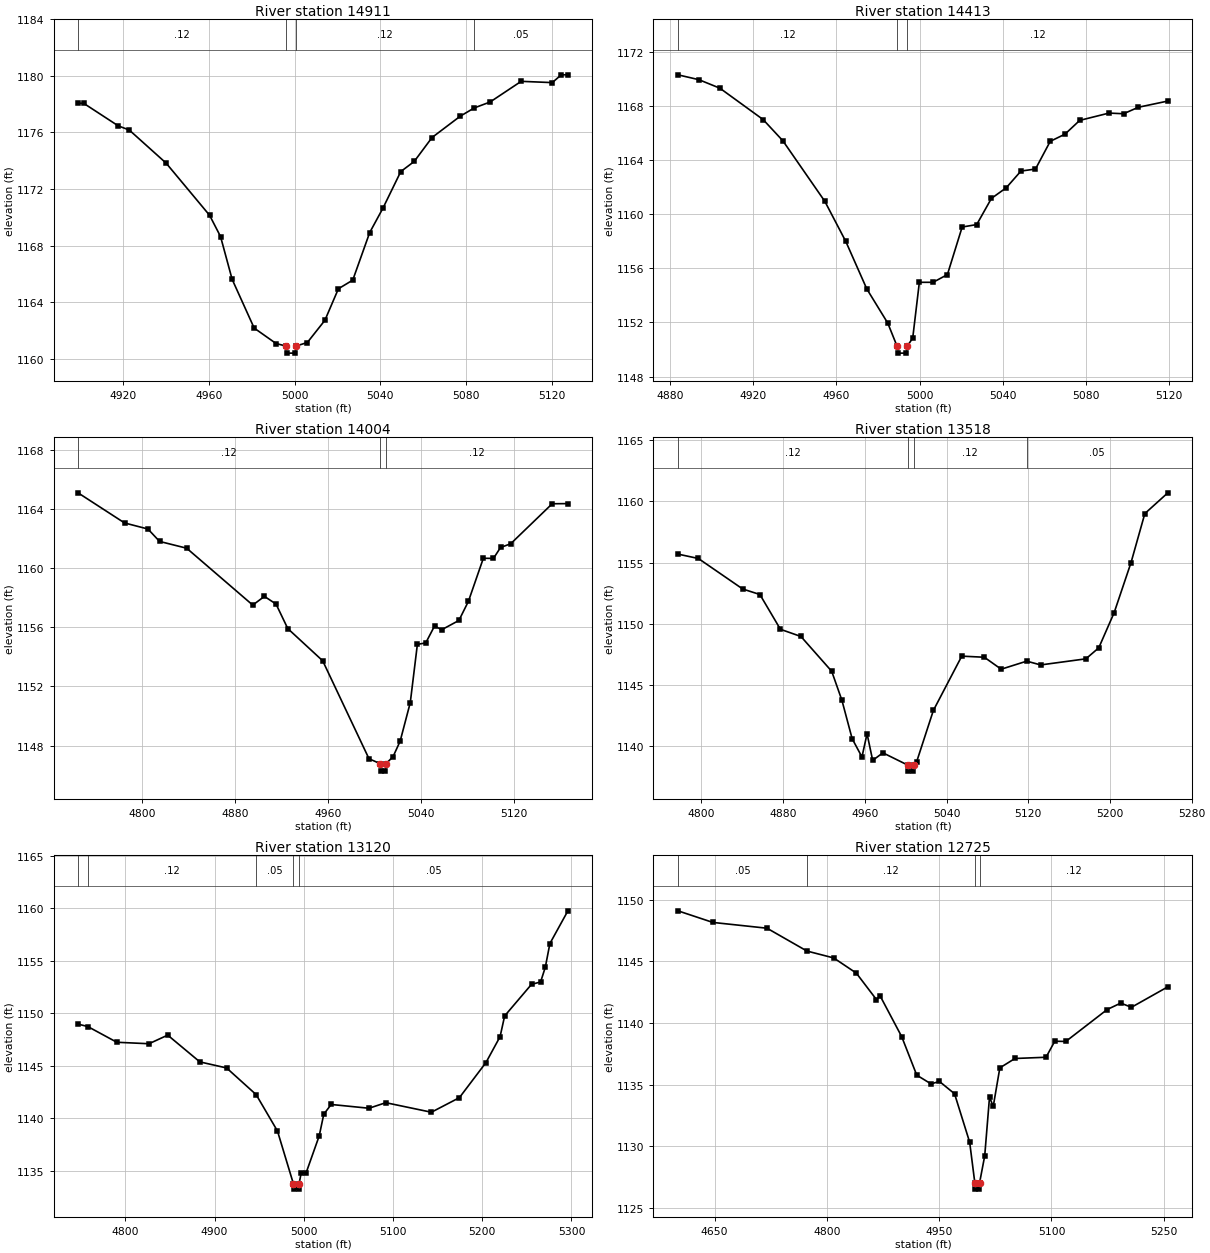
Type RM Length L Ch R = 1 ,14911   ,498,498,498
BEGIN DESCRIPTION:
CEDAR HOLLOW CREEK 32.0
END DESCRIPTION:
XS GIS Cut Line= 3
      2853905.72      10281253.1      2853807.25       10281276.
       2853705.7      10281353.1
#Sta/Elev= 30
  4898.9 1178.06  4901.5 1178.06  4917.7 1176.46  4922.8 1176.17    4940 1173.83
  4960.3 1170.14  4965.4 1168.64  4970.8 1165.62  4981.1 1162.17  4991.3 1161.08
  4995.9  1160.9  4996.2  1160.4  5000.3  1160.4  5000.6  1160.9  5005.9 1161.15
  5014.1 1162.72  5020.4 1164.95  5027.1 1165.56    5035 1168.92  5041.2 1170.65
  5049.5 1173.23  5055.8 1173.95  5064.1 1175.64  5077.3 1177.15  5083.8 1177.73
  5091.2 1178.15  5105.7 1179.61  5120.2 1179.52  5124.4 1180.07  5127.5 1180.07
#Mann= 4 ,-1 , 0
  4898.9     .12       0  4995.9     .07       0  5000.6     .12       0
  5083.8     .05       0
Bank Sta=4995.9,5000.6
XS Rating Curve= 0 ,0
Exp/Cntr=0.3,0.1

Type RM Length L Ch R = 1 ,14413   ,409,409,409
BEGIN DESCRIPTION:
CEDAR HOLLOW CREEK 31.0
END DESCRIPTION:
XS GIS Cut Line= 3
      2853755.71     10280803.11       2853640.5       10280819.
      2853555.65     10280903.15
#Sta/Elev= 30
  4883.7 1170.32  4893.8 1169.96  4903.9 1169.33  4924.7 1167.01  4934.2 1165.44
  4954.4 1160.96  4964.5 1157.99  4974.6 1154.48  4984.7 1151.95  4989.2 1150.23
  4989.6 1149.73  4993.7 1149.73    4994 1150.23  4996.7 1150.84  4999.9 1154.97
  5006.5 1154.97  5013.4 1155.54  5020.5 1159.06  5027.5 1159.24  5034.6 1161.18
  5041.7 1161.96  5048.8  1163.2  5055.8 1163.35  5062.9  1165.4    5070 1165.93
  5077.1 1166.95  5091.2 1167.49  5098.2 1167.44  5105.3 1167.92  5119.5 1168.38
#Mann= 3 ,-1 , 0
  4883.7     .12       0  4989.2     .07       0    4994     .12       0
Bank Sta=4989.2,4994
XS Rating Curve= 0 ,0
Exp/Cntr=0.3,0.1

Type RM Length L Ch R = 1 ,14004   ,486,486,486
BEGIN DESCRIPTION:
CEDAR HOLLOW CREEK 30.0
END DESCRIPTION:
XS GIS Cut Line= 3
      2853655.67     10280503.11      2853401.25       10280517.
      2853305.69      10280653.1
#Sta/Elev= 30
  4745.2 1165.11  4785.2 1163.07  4805.3 1162.66  4815.3 1161.82  4838.6 1161.36
  4895.4 1157.51  4905.4  1158.1  4915.4 1157.58  4925.5 1155.92  4955.5 1153.74
  4995.3 1147.11  5005.1 1146.77  5005.4 1146.27  5009.5 1146.27  5009.9 1146.77
    5016 1147.25  5022.1  1148.3  5030.8 1150.91  5036.9 1154.85  5044.1 1154.95
  5051.7  1156.1  5057.8 1155.84  5072.6 1156.47  5080.8 1157.77  5093.6 1160.68
  5102.3 1160.67  5108.4 1161.41  5117.1 1161.66  5152.8 1164.37  5166.3 1164.38
#Mann= 3 ,-1 , 0
  4745.2     .12       0  5005.1     .07       0  5009.9     .12       0
Bank Sta=5005.1,5009.9
XS Rating Curve= 0 ,0
Exp/Cntr=0.3,0.1

Type RM Length L Ch R = 1 ,13518   ,398,398,398
BEGIN DESCRIPTION:
CEDAR HOLLOW CREEK 29.0
END DESCRIPTION:
XS GIS Cut Line= 3
      2853355.66     10280153.11       2853133.5       10280135.
       2852905.7     10280253.11
#Sta/Elev= 30
  4777.1 1155.69  4797.1 1155.33  4840.5 1152.83  4857.3 1152.38  4877.4 1149.53
  4897.5 1148.94  4927.6 1146.09  4937.6 1143.71  4947.6 1140.57  4957.2 1139.07
  4962.2 1140.97  4967.7 1138.79  4977.7 1139.41  5001.9 1138.41  5002.4 1137.91
  5007.6 1137.91  5008.1 1138.41  5010.6 1138.64  5027.1 1142.88  5054.9 1147.33
    5077 1147.24  5093.5 1146.26  5118.5 1146.92  5132.1 1146.61  5176.4 1147.11
    5189 1148.01  5204.1  1150.9  5220.6    1155  5234.1 1159.01  5256.6 1160.71
#Mann= 4 ,-1 , 0
  4777.1     .12       0  5001.9     .07       0  5008.1     .12       0
  5118.5     .05       0
Bank Sta=5001.9,5008.1
XS Rating Curve= 0 ,0
Exp/Cntr=0.3,0.1

Type RM Length L Ch R = 1 ,13120   ,395,395,395
BEGIN DESCRIPTION:
CEDAR HOLLOW CREEK 28.0
END DESCRIPTION:
XS GIS Cut Line= 3
      2853005.71     10279653.07       2852864.5       10279863.
      2852805.69      10280153.1
#Sta/Elev= 30
    4747 1148.96  4757.9 1148.73  4790.5 1147.23  4826.5 1147.09  4847.5 1147.91
  4883.5 1145.36  4913.5 1144.78  4946.6 1142.24  4970.5 1138.77  4988.4 1133.73
  4988.9 1133.23  4994.2 1133.23  4994.7 1133.73  4997.1 1134.78  5002.6 1134.78
  5017.3 1138.31  5022.4 1140.37  5030.7  1141.3  5073.1 1140.94  5091.9 1141.47
    5143 1140.56  5174.4 1141.95  5204.2  1145.3    5220 1147.77  5225.1 1149.74
  5255.2 1152.75  5265.4 1152.98  5270.7 1154.39  5275.8 1156.64    5296 1159.76
#Mann= 5 ,-1 , 0
    4747     .05       0  4757.9     .12       0  4946.6     .05       0
  4988.4     .05       0  4994.7     .05       0
Bank Sta=4988.4,4994.7
XS Rating Curve= 0 ,0
Exp/Cntr=0.3,0.1

Type RM Length L Ch R = 1 ,12725   ,251,251,251
BEGIN DESCRIPTION:
CEDAR HOLLOW CREEK 27.0
END DESCRIPTION:
XS GIS Cut Line= 3
      2853091.91     10279482.77      2852604.51     10279547.95
      2852555.68     10279703.11
#Sta/Elev= 30
    4601 1149.09  4647.6 1148.15    4720 1147.68  4773.3 1145.83  4809.1 1145.27
  4839.3 1144.04  4866.1  1141.9  4871.1 1142.19  4899.9 1138.89    4920 1135.77
  4939.1 1135.06  4950.3 1135.26  4970.5 1134.26  4990.7 1130.33  4997.6 1127.03
  4998.1 1126.53  5003.4 1126.53  5003.9 1127.03  5010.8 1129.23  5017.2 1133.98
  5022.2 1133.24    5031 1136.36  5051.2 1137.12  5092.7 1137.22  5104.4 1138.52
  5119.1  1138.5  5174.4 1141.09  5192.5 1141.61  5206.8 1141.27  5255.4 1142.93
#Mann= 4 ,-1 , 0
    4601     .05       0  4773.3     .12       0  4997.6     .07       0
  5003.9     .12       0
Bank Sta=4997.6,5003.9
XS Rating Curve= 0 ,0
Exp/Cntr=0.3,0.1

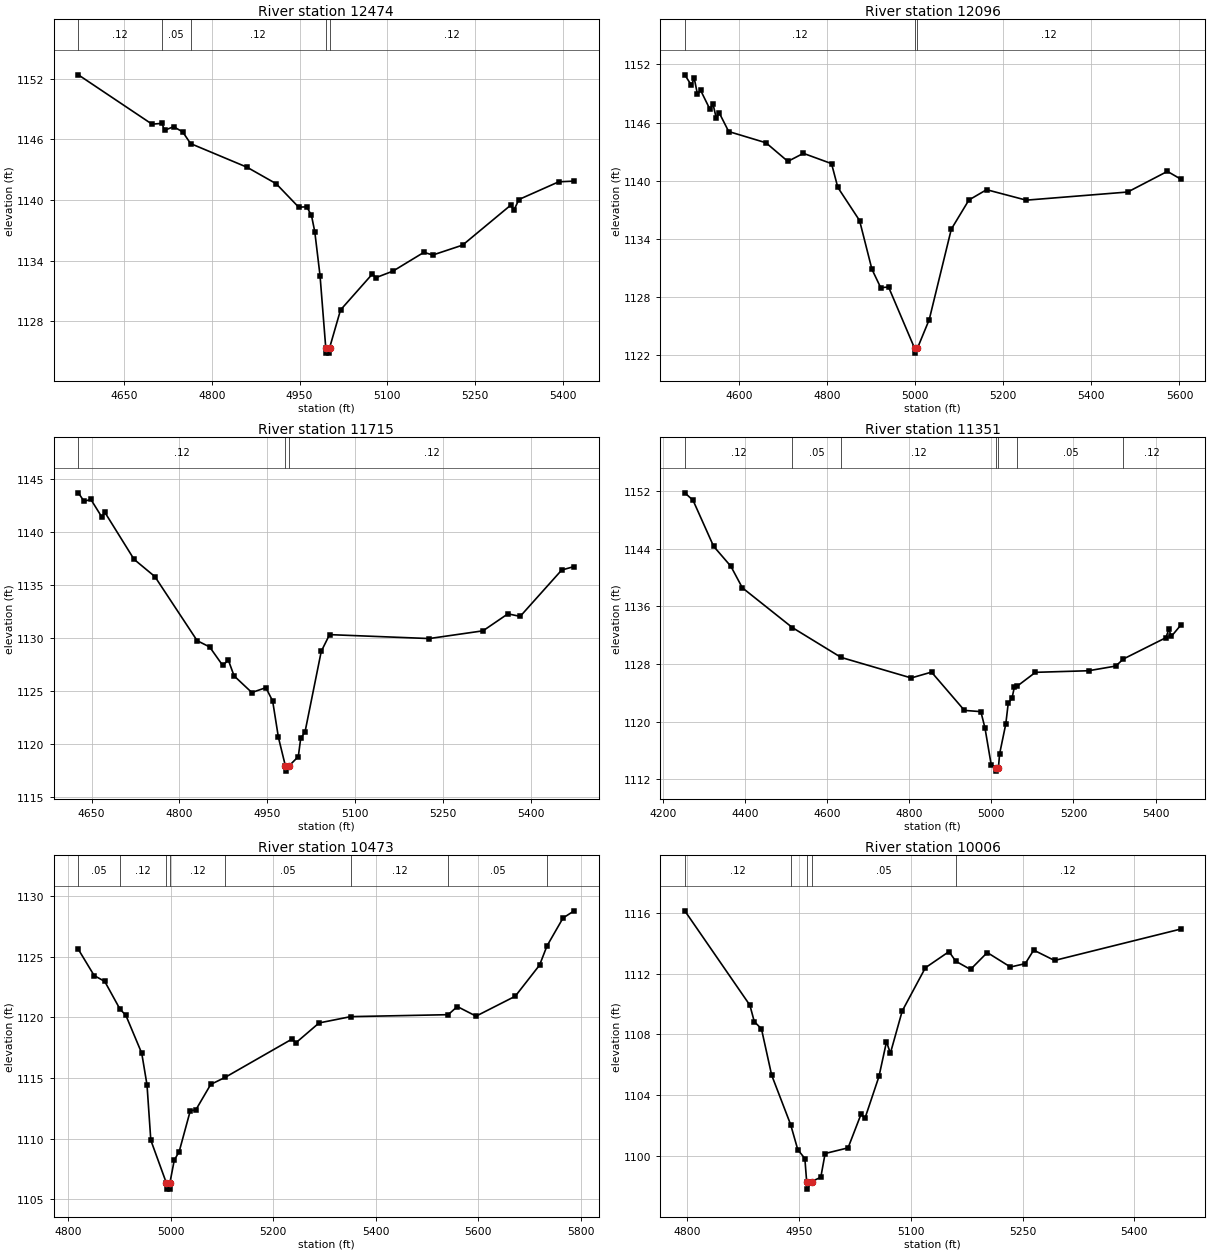
Type RM Length L Ch R = 1 ,12474   ,378,378,378
BEGIN DESCRIPTION:
CEDAR HOLLOW CREEK 26.0
END DESCRIPTION:
XS GIS Cut Line= 3
      2852968.93     10279013.19      2852746.72     10279147.99
      2852471.21     10279666.43
#Sta/Elev= 30
  4572.1 1152.39    4698 1147.51  4714.9 1147.59  4719.3  1146.9  4734.8 1147.26
  4750.3 1146.75  4763.9 1145.59  4860.4 1143.25  4910.1 1141.62  4948.4 1139.31
  4962.4 1139.33  4970.4 1138.48    4976 1136.88    4985 1132.53  4994.8 1125.37
  4995.3 1124.87  5000.7 1124.87  5001.2 1125.37    5020 1129.14  5074.6 1132.71
  5080.3 1132.33  5109.6 1132.98  5162.5 1134.84  5177.5 1134.57  5228.5 1135.55
  5310.7  1139.5  5316.4 1139.02  5324.7 1140.06  5392.7 1141.81  5419.1 1141.88
#Mann= 5 ,-1 , 0
  4572.1     .12       0  4714.9     .05       0  4763.9     .12       0
  4994.8     .07       0  5001.2     .12       0
Bank Sta=4994.8,5001.2
XS Rating Curve= 0 ,0
Exp/Cntr=0.3,0.1

Type RM Length L Ch R = 1 ,12096   ,381,381,381
BEGIN DESCRIPTION:
Mapping XS 1ec2e0b7
END DESCRIPTION:
XS GIS Cut Line= 3
      2852603.03     10278999.86      2852323.06     10279296.13
      2852293.43     10280013.09
#Sta/Elev= 30
  4477.4 1150.92  4492.1 1149.86  4498.9 1150.55  4506.2  1148.9  4513.1 1149.34
  4534.5 1147.36  4541.4 1147.91  4548.7 1146.47  4555.6 1146.99    4577 1145.07
  4661.6 1143.91  4711.3 1141.99  4746.5 1142.82  4810.4 1141.76  4824.6 1139.31
    4874 1135.89    4902 1130.87    4922 1128.96  4939.8 1129.03  4998.9 1122.71
  4999.4 1122.21  5005.3 1122.71  5032.1 1125.67  5082.2    1135  5122.2 1138.01
  5162.3 1139.07  5252.3 1137.99  5482.5 1138.83  5572.6 1140.96  5602.6 1140.17
#Mann= 3 ,-1 , 0
  4477.4     .12       0  4998.9     .07       0  5005.3     .12       0
Bank Sta=4998.9,5005.3
XS Rating Curve= 0 ,0
Exp/Cntr=0.3,0.1

Type RM Length L Ch R = 1 ,11715   ,364,364,364
BEGIN DESCRIPTION:
CEDAR HOLLOW CREEK 25.0
END DESCRIPTION:
XS GIS Cut Line= 3
      2852355.71      10279103.1      2852006.75       10279234.
       2851655.7     10279553.09
#Sta/Elev= 30
  4627.3 1143.66  4637.1 1142.86  4648.7 1143.04  4667.4 1141.38  4672.7 1141.81
  4722.5 1137.39  4758.1 1135.76  4830.3 1129.72  4851.6 1129.13  4873.8  1127.4
  4883.7 1127.87  4893.4  1126.4  4923.7 1124.83  4947.7 1125.29  4959.3 1124.03
  4969.1 1120.61    4981 1117.92  4981.5 1117.42  4987.4 1117.92  5003.1 1118.79
  5007.2  1120.5  5014.6 1121.12  5042.3 1128.71  5056.5 1130.29  5226.8 1129.92
  5318.7 1130.65  5361.2 1132.25  5382.2 1132.01  5453.1 1136.38  5474.4 1136.71
#Mann= 3 ,-1 , 0
  4627.3     .12       0    4981     .07       0  4987.4     .12       0
Bank Sta=4981,4987.4
XS Rating Curve= 0 ,0
Exp/Cntr=0.3,0.1

Type RM Length L Ch R = 1 ,11351   ,878,878,878
BEGIN DESCRIPTION:
CEDAR HOLLOW CREEK 24.0
END DESCRIPTION:
XS GIS Cut Line= 3
      2852505.67     10279003.11      2851760.25       10278969.
      2851505.69      10279353.1
#Sta/Elev= 30
  4253.8 1151.73  4273.8  1150.7  4323.9 1144.32    4366 1141.54  4393.9 1138.56
  4515.5 1133.05  4634.2 1128.91    4805 1126.06  4854.4 1126.87  4934.5 1121.56
  4974.5 1121.39  4984.5 1119.13  4999.8 1113.98  5010.9 1113.64  5011.4 1113.14
  5017.3 1113.64  5020.1 1115.52  5035.2 1119.68  5041.2 1122.58  5050.2 1123.22
  5056.2 1124.82  5063.1 1124.93  5107.4 1126.84  5236.7 1127.06  5302.9 1127.71
  5321.5 1128.69  5424.8 1131.64  5432.2  1132.8  5438.2 1131.82  5460.8 1133.36
#Mann= 7 ,-1 , 0
  4253.8     .12       0  4515.5     .05       0  4634.2     .12       0
  5010.9     .07       0  5017.3     .12       0  5063.1     .05       0
  5321.5     .12       0
Bank Sta=5010.9,5017.3
XS Rating Curve= 0 ,0
Exp/Cntr=0.3,0.1

Type RM Length L Ch R = 1 ,10473   ,467,467,467
BEGIN DESCRIPTION:
CEDAR HOLLOW CREEK 23.0
END DESCRIPTION:
XS GIS Cut Line= 3
      2851755.68     10278153.13      2851711.75       10278328.
      2851405.67     10279053.15
#Sta/Elev= 30
  4819.7 1125.59  4850.6 1123.43  4871.2 1122.95  4900.8 1120.68  4912.5 1120.15
  4943.4 1117.04  4953.7 1114.43  4961.1 1109.88  4991.5 1106.35    4992 1105.85
  4997.8 1105.85  4998.3 1106.35  5006.9 1108.24  5016.4 1108.93  5038.1  1112.3
  5048.9 1112.37    5078 1114.47  5105.7 1115.04  5236.5  1118.2  5244.3  1117.9
  5289.4 1119.53  5351.2 1120.05  5541.3 1120.21  5559.1 1120.88  5595.7 1120.09
  5672.2 1121.73  5719.6 1124.29  5734.1 1125.87  5765.4 1128.17  5787.1 1128.76
#Mann= 8 ,-1 , 0
  4819.7     .05       0  4900.8     .12       0  4991.5     .07       0
  4998.3     .12       0  5105.7     .05       0  5351.2     .12       0
  5541.3     .05       0  5734.1     .12       0
Bank Sta=4991.5,4998.3
XS Rating Curve= 0 ,0
Exp/Cntr=0.3,0.1

Type RM Length L Ch R = 1 ,10006   ,467,467,467
BEGIN DESCRIPTION:
CEDAR HOLLOW CREEK 22.0
END DESCRIPTION:
XS GIS Cut Line= 3
      2851455.65     10278053.13      2851281.25       10278158.
      2851405.69     10278603.13
#Sta/Elev= 30
  4796.5 1116.12  4883.9 1109.92  4889.8 1108.84  4899.4 1108.37  4913.1 1105.33
  4938.6 1102.08  4948.2 1100.43  4957.7 1099.85  4960.1 1098.34  4960.6 1097.84
  4966.9 1098.34  4979.1 1098.62  4984.9 1100.18  5015.7 1100.55  5033.2 1102.77
  5038.3 1102.48  5057.2 1105.24  5067.3 1107.52  5072.5 1106.76  5088.4 1109.54
  5119.5 1112.38  5151.2 1113.44  5160.3 1112.81  5180.1 1112.27  5202.6 1113.38
  5233.7 1112.43  5253.6 1112.65  5264.9 1113.54  5292.9 1112.86  5462.2 1114.92
#Mann= 5 ,-1 , 0
  4796.5     .12       0  4938.6     .05       0  4960.1     .05       0
  4966.9     .05       0  5160.3     .12       0
Bank Sta=4960.1,4966.9
XS Rating Curve= 0 ,0
Exp/Cntr=0.3,0.1