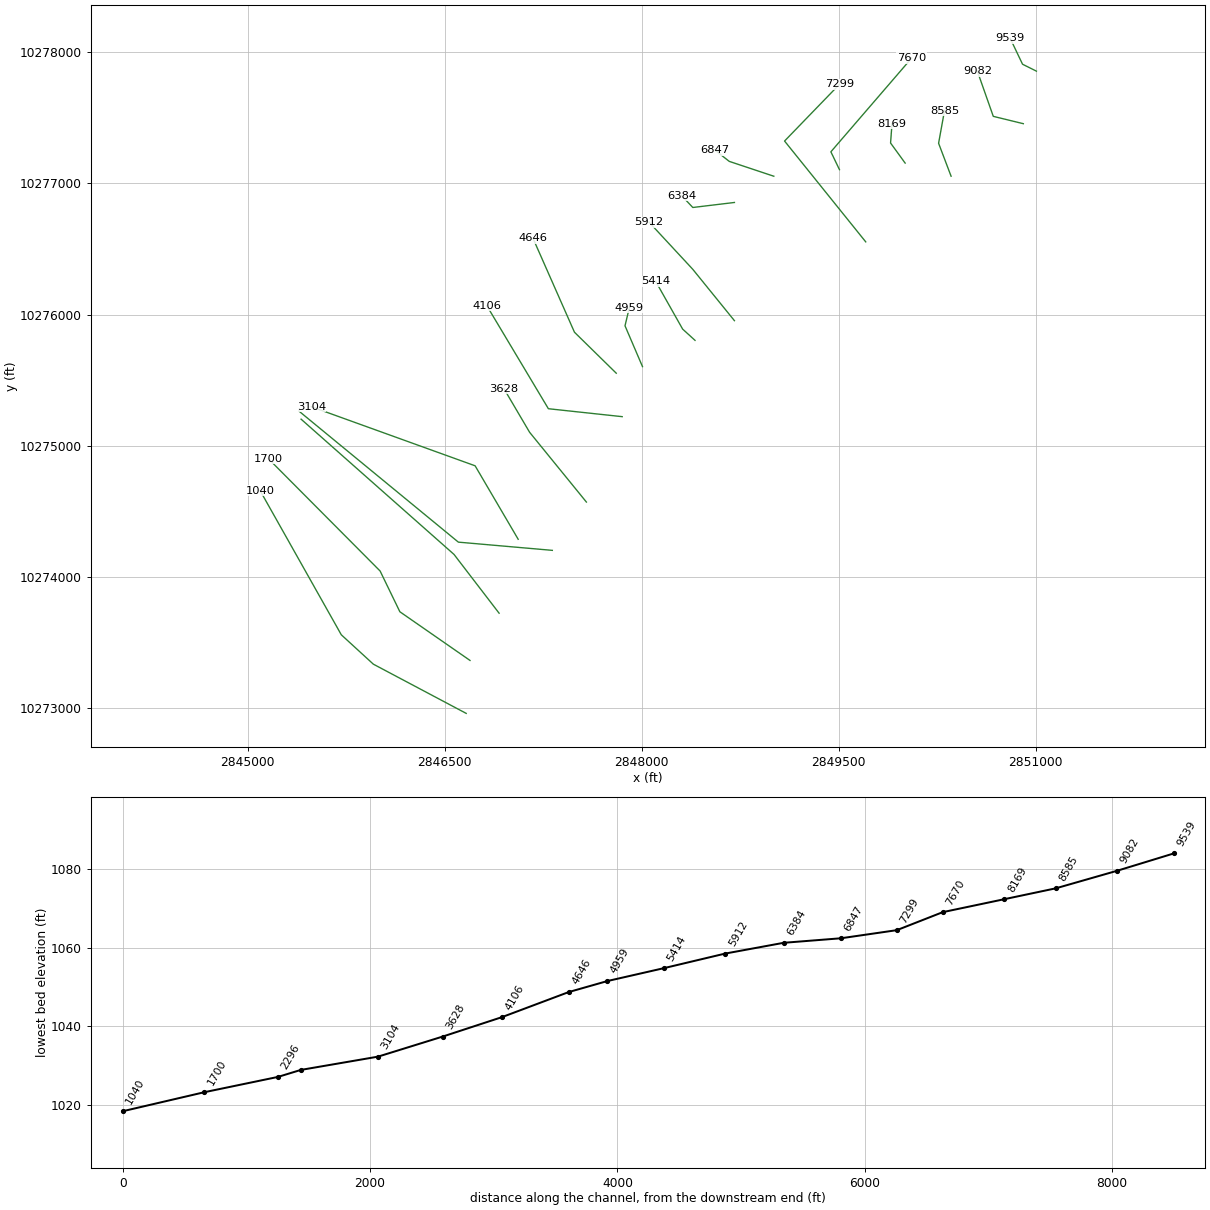
HEC-RAS study CEDAR HOLLOW CREEK.prj: CEDAR HOLLOW CREEK Base Level Engineering

--- CEDAR HOLLOW CREEK.g01 (geometry) --- (continued)

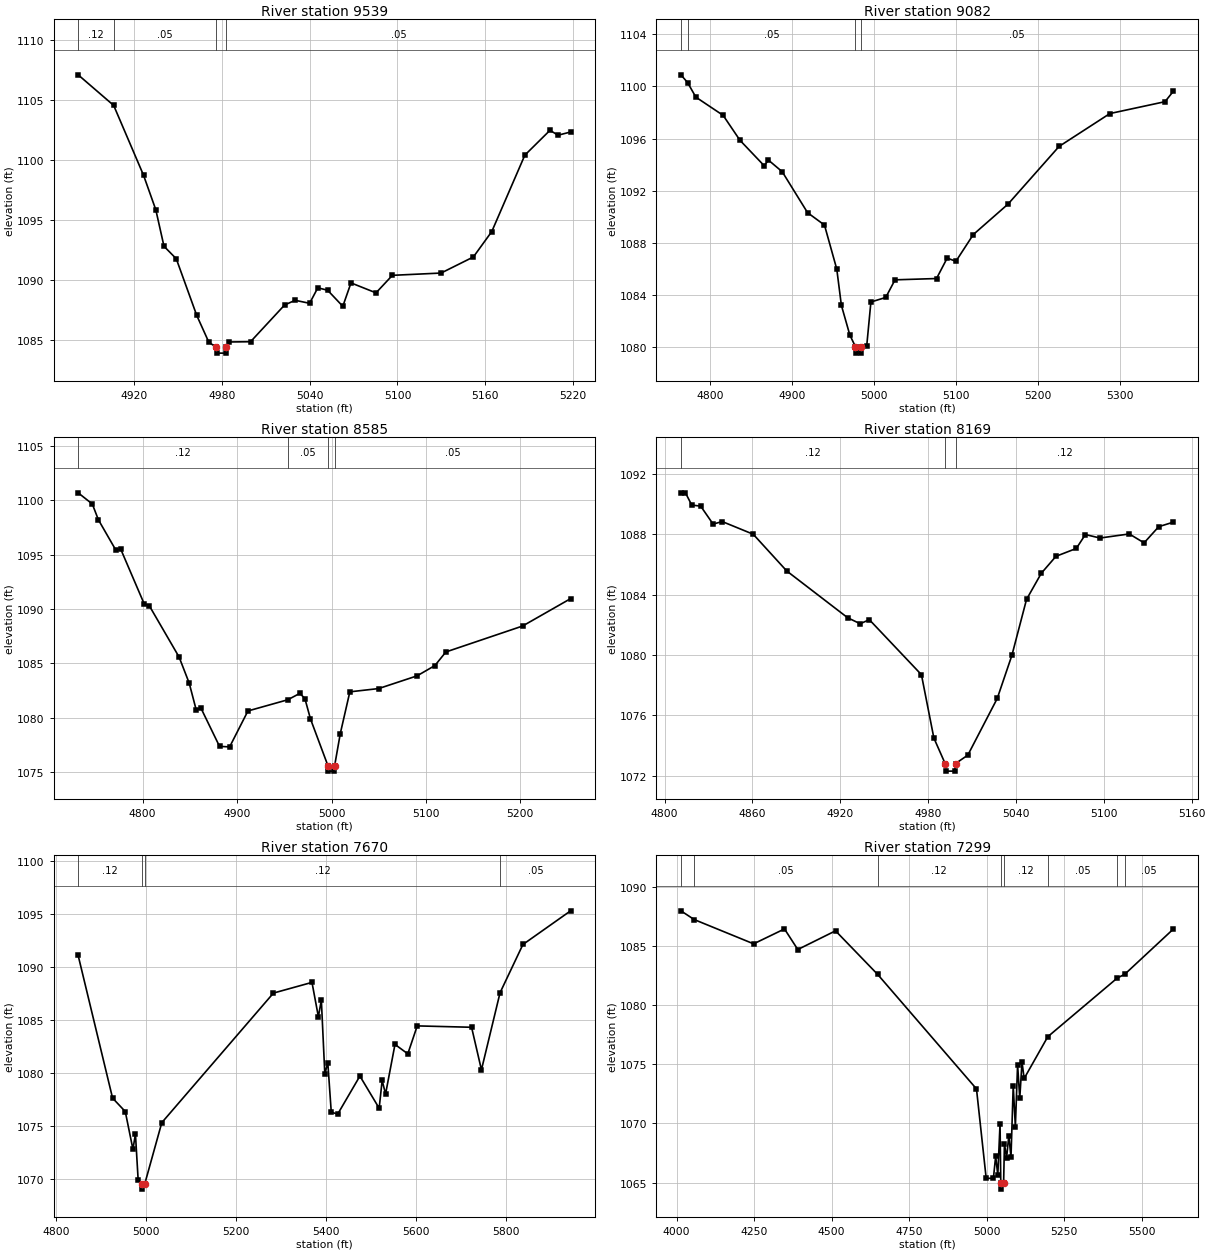
Type RM Length L Ch R = 1 ,9539    ,457,457,457
BEGIN DESCRIPTION:
CEDAR HOLLOW CREEK 21.0
END DESCRIPTION:
XS GIS Cut Line= 3
      2851005.68     10277853.11      2850899.75       10277906.
      2850805.69     10278103.11
#Sta/Elev= 30
  4881.6 1107.12  4905.9 1104.57  4926.3 1098.76  4934.7 1095.88  4940.3 1092.84
  4948.7  1091.8  4962.7 1087.08    4971 1084.84    4976 1084.44  4976.5 1083.94
  4982.4 1083.94  4982.9 1084.44  4985.1 1084.87  4999.5 1084.89  5022.8 1087.95
    5030 1088.34  5039.9 1088.09  5045.5 1089.38  5052.2 1089.18  5062.6 1087.84
  5068.2 1089.79  5085.3 1088.96  5096.5 1090.42  5129.8 1090.61  5151.9 1091.95
  5164.5 1094.07  5187.1 1100.43  5204.3  1102.5  5209.8 1102.09  5218.4 1102.36
#Mann= 4 ,-1 , 0
  4881.6     .12       0  4905.9     .05       0    4976     .05       0
  4982.9     .05       0
Bank Sta=4976,4982.9
XS Rating Curve= 0 ,0
Exp/Cntr=0.3,0.1

Type RM Length L Ch R = 1 ,9082    ,497,497,497
BEGIN DESCRIPTION:
CEDAR HOLLOW CREEK 20.0
END DESCRIPTION:
XS GIS Cut Line= 3
      2850905.67     10277453.12        2850677.       10277509.
      2850555.67     10277853.14
#Sta/Elev= 30
  4764.6 1100.89  4772.7  1100.3  4782.8 1099.18  4816.1 1097.78  4836.6 1095.87
  4866.1 1093.92  4871.3 1094.35  4888.1 1093.46    4919 1090.32  4939.6 1089.37
  4954.6 1085.99  4960.2 1083.22  4970.5 1080.94  4977.3 1080.05  4977.8 1079.55
  4983.8 1079.55  4984.3 1080.05  4991.1  1080.1  4996.2 1083.47  5014.3 1083.82
  5025.6 1085.17  5076.2 1085.27  5089.2 1086.84  5099.8 1086.59    5121 1088.64
  5163.4 1090.98  5225.6  1095.4  5287.5 1097.92  5354.7 1098.83  5364.9 1099.63
#Mann= 4 ,-1 , 0
  4764.6     .12       0  4772.7     .05       0  4977.3     .05       0
  4984.3     .05       0
Bank Sta=4977.3,4984.3
XS Rating Curve= 0 ,0
Exp/Cntr=0.3,0.1

Type RM Length L Ch R = 1 ,8585    ,416,416,416
BEGIN DESCRIPTION:
CEDAR HOLLOW CREEK 19.0
END DESCRIPTION:
XS GIS Cut Line= 3
      2850355.67     10277053.15       2850260.5       10277304.
      2850305.69     10277553.13
#Sta/Elev= 30
  4731.7  1100.7  4746.7 1099.67  4753.1 1098.22  4771.5 1095.44  4776.9 1095.49
  4801.7 1090.46    4807 1090.31  4838.6 1085.58  4849.3 1083.18  4856.6 1080.75
  4861.9 1080.85  4881.4 1077.36  4892.1 1077.31  4911.5 1080.62  4953.7 1081.65
  4966.5 1082.24  4971.8 1081.76  4977.7 1079.89  4996.2 1075.58  4996.7 1075.08
  5002.8 1075.08  5003.3 1075.58  5009.3 1078.54  5019.4 1082.38  5049.9 1082.68
  5090.6 1083.85  5109.5  1084.8  5121.1 1086.05  5202.4 1088.44  5253.2 1090.96
#Mann= 4 ,-1 , 0
  4731.7     .12       0  4953.7     .05       0  4996.2     .03       0
  5003.3     .05       0
Bank Sta=4996.2,5003.3
XS Rating Curve= 0 ,0
Exp/Cntr=0.3,0.1

Type RM Length L Ch R = 1 ,8169    ,499,499,499
BEGIN DESCRIPTION:
CEDAR HOLLOW CREEK 18.0
END DESCRIPTION:
XS GIS Cut Line= 3
      2850005.69     10277153.11      2849894.75       10277306.
      2849905.68     10277453.09
#Sta/Elev= 30
  4811.1 1090.73  4814.2 1090.73  4818.5 1089.92  4824.6 1089.85  4833.1 1088.66
  4839.3 1088.83  4860.5 1087.99  4883.4 1085.56  4925.1 1082.46  4933.6 1082.07
  4939.8 1082.34  4975.4  1078.7  4983.9 1074.51  4991.6 1072.82  4992.1 1072.32
  4998.2 1072.32  4998.7 1072.82  5007.1 1073.38  5027.2 1077.13  5037.2 1079.98
  5047.2 1083.68  5057.3 1085.41  5067.3 1086.53  5081.2 1087.05  5087.4 1087.97
  5097.4 1087.74  5117.4 1088.01  5127.5 1087.42  5137.5 1088.49  5147.5 1088.79
#Mann= 3 ,-1 , 0
  4811.1     .12       0  4991.6     .07       0  4998.7     .12       0
Bank Sta=4991.6,4998.7
XS Rating Curve= 0 ,0
Exp/Cntr=0.3,0.1

Type RM Length L Ch R = 1 ,7670    ,371,371,371
BEGIN DESCRIPTION:
CEDAR HOLLOW CREEK 17.0
END DESCRIPTION:
XS GIS Cut Line= 3
      2849505.67     10277103.13      2849440.25       10277239.
      2850055.67      10277953.1
#Sta/Elev= 30
  4849.2 1091.09  4925.6 1077.62  4953.8 1076.35  4970.8 1072.79  4976.4 1074.22
  4982.4 1069.89  4989.9 1069.52  4990.4 1069.02  4997.1 1069.52  5034.9  1075.3
  5282.8 1087.54  5368.4 1088.55  5382.6 1085.31  5389.2 1086.88  5396.9 1079.89
  5403.5 1080.98  5411.2  1076.3  5425.4  1076.1  5474.8  1079.7  5517.6 1076.66
  5524.2 1079.29  5531.8    1078  5552.7 1082.69  5581.2  1081.8  5602.1 1084.44
  5722.8 1084.31  5744.7 1080.29    5786 1087.57  5836.8 1092.13  5942.7 1095.31
#Mann= 4 ,-1 , 0
  4849.2     .12       0  4989.9     .07       0  4997.1     .12       0
    5786     .05       0
Bank Sta=4989.9,4997.1
XS Rating Curve= 0 ,0
Exp/Cntr=0.3,0.1

Type RM Length L Ch R = 1 ,7299    ,452,452,452
BEGIN DESCRIPTION:
CEDAR HOLLOW CREEK 16.0
END DESCRIPTION:
XS GIS Cut Line= 3
      2849705.68     10276553.11       2849087.5       10277321.
      2849505.66     10277753.09
#Sta/Elev= 30
  4014.2 1087.97  4057.2 1087.23  4248.6 1085.18    4348 1086.44  4390.9  1084.7
  4512.5 1086.28  4648.5 1082.59  4966.8 1072.92  4998.1 1065.35  5021.4 1065.38
  5028.6 1067.23  5035.5 1065.63  5042.7 1069.98  5045.1 1064.95  5045.6 1064.45
  5054.2 1064.95  5056.9  1068.3  5063.8 1067.08    5071 1068.98    5078 1067.13
  5085.2 1073.19  5092.1 1069.72  5099.3 1074.97  5106.3 1072.13  5113.5 1075.19
  5120.4  1073.8  5196.6 1077.33  5420.5 1082.29  5444.7 1082.61  5601.3 1086.43
#Mann= 8 ,-1 , 0
  4014.2     .12       0  4057.2     .05       0  4648.5     .12       0
  5045.1     .07       0  5054.2     .12       0  5196.6     .05       0
  5420.5     .12       0  5444.7     .05       0
Bank Sta=5045.1,5054.2
XS Rating Curve= 0 ,0
Exp/Cntr=0.3,0.1

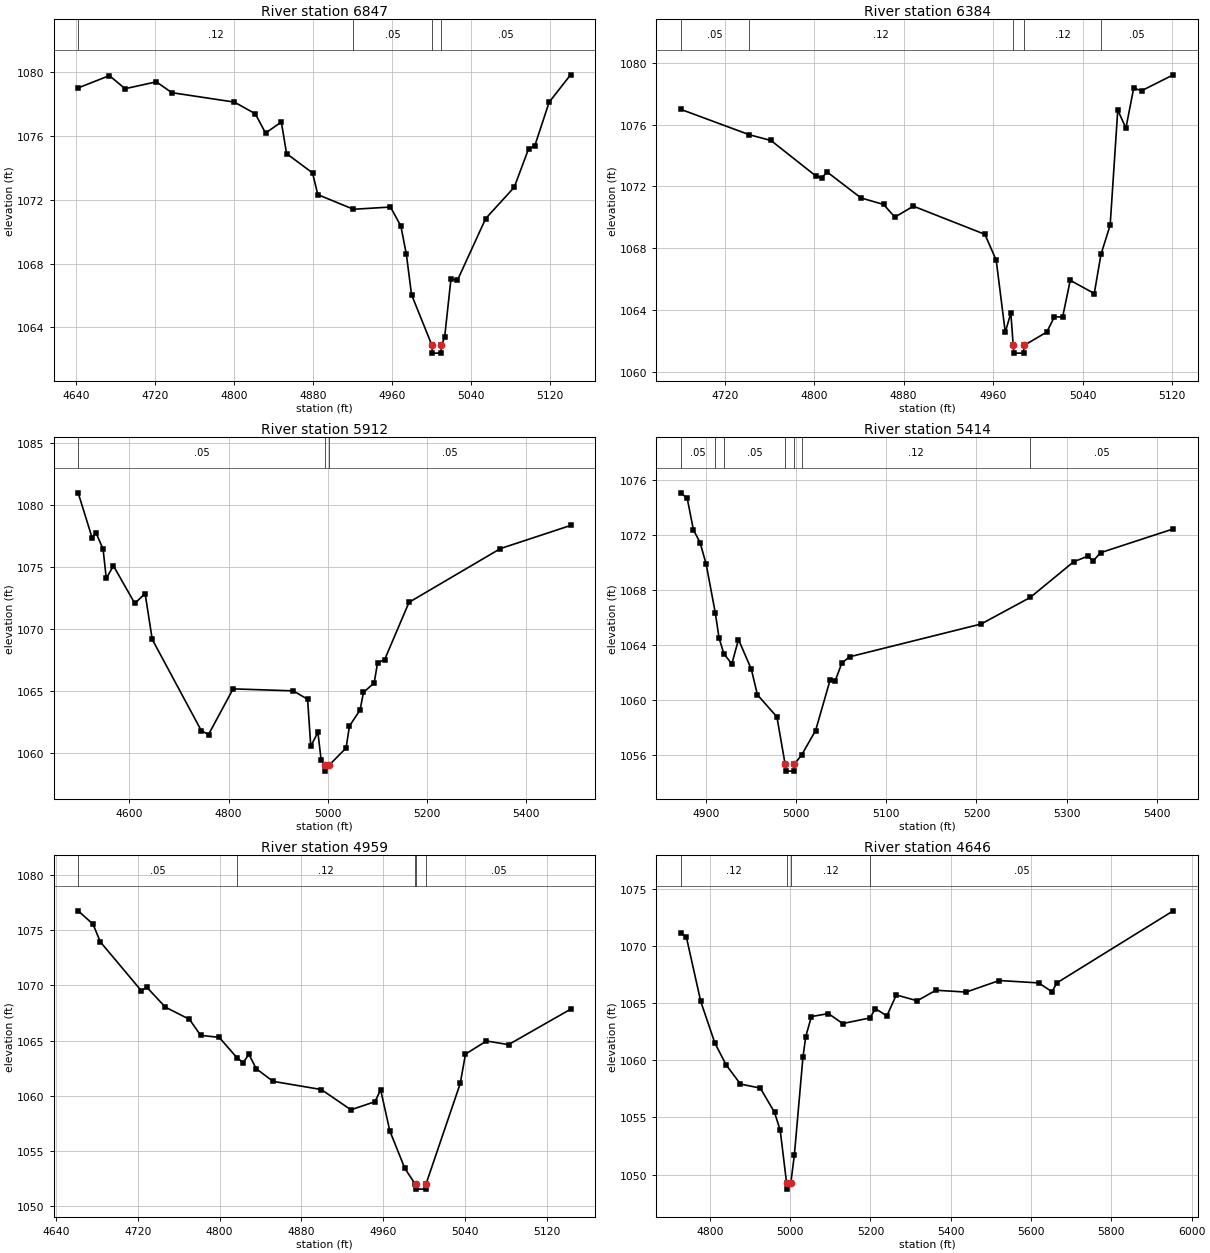
Type RM Length L Ch R = 1 ,6847    ,463,463,463
BEGIN DESCRIPTION:
CEDAR HOLLOW CREEK 15.0
END DESCRIPTION:
XS GIS Cut Line= 3
      2849005.71      10277053.1       2848666.5       10277166.
      2848555.65     10277253.14
#Sta/Elev= 30
  4642.5 1079.02  4674.1 1079.79    4690 1078.97  4721.6  1079.4  4737.4 1078.72
  4800.6 1078.13  4821.8  1077.4  4832.2 1076.19  4848.2 1076.88  4853.5  1074.9
  4879.8 1073.69  4885.1 1072.33  4921.2 1071.41  4958.7 1071.55  4969.2 1070.36
  4974.8 1068.58    4980 1066.06  5000.6 1062.89  5001.1 1062.39  5009.8 1062.39
  5010.3 1062.89  5013.5 1063.37  5019.9 1067.03  5026.5 1066.96  5055.1 1070.83
    5084 1072.79  5098.5  1075.2  5104.8 1075.39  5119.3 1078.12    5141 1079.84
#Mann= 4 ,-1 , 0
  4642.5     .12       0  4921.2     .05       0  5000.6     .05       0
  5010.3     .05       0
Bank Sta=5000.6,5010.3
XS Rating Curve= 0 ,0
Exp/Cntr=0.3,0.1

Type RM Length L Ch R = 1 ,6384    ,472,472,472
BEGIN DESCRIPTION:
CEDAR HOLLOW CREEK 14.0
END DESCRIPTION:
XS GIS Cut Line= 3
      2848705.67     10276853.11      2848388.75       10276815.
      2848305.68     10276903.12
#Sta/Elev= 30
  4680.8 1076.98  4742.1 1075.34  4761.4 1074.97  4801.5 1072.68  4806.6 1072.56
  4811.7 1072.93  4841.9 1071.26  4862.1 1070.84  4872.2 1070.02  4888.7 1070.73
  4952.7 1068.91  4962.8 1067.24  4970.9 1062.59  4975.9 1063.83    4978 1061.74
  4978.5 1061.24  4987.3 1061.24  4987.8 1061.74    5008  1062.6  5014.9 1063.59
  5022.2 1063.57    5029 1065.94  5050.5 1065.09  5056.5 1067.62  5064.7  1069.5
  5071.5 1076.93  5078.8 1075.77  5085.7 1078.34    5093 1078.19  5121.1 1079.21
#Mann= 5 ,-1 , 0
  4680.8     .05       0  4742.1     .12       0    4978     .07       0
  4987.8     .12       0  5056.5     .05       0
Bank Sta=4978,4987.8
XS Rating Curve= 0 ,0
Exp/Cntr=0.3,0.1

Type RM Length L Ch R = 1 ,5912    ,498,498,498
BEGIN DESCRIPTION:
CEDAR HOLLOW CREEK 13.0
END DESCRIPTION:
XS GIS Cut Line= 3
      2848705.66     10275953.14      2848388.75       10276344.
      2848055.68     10276703.12
#Sta/Elev= 30
  4496.8 1081.01  4524.8 1077.39  4532.7 1077.79  4547.1 1076.45  4553.5 1074.09
  4567.9 1075.11    4611 1072.07  4631.8 1072.87  4646.2 1069.16  4745.3 1061.77
  4759.7 1061.47  4809.3 1065.16  4930.7    1065  4959.5 1064.32  4965.9 1060.52
  4980.3 1061.65  4986.7 1059.45  4993.6 1059.01  4994.1 1058.51  5003.4 1059.01
  5037.1 1060.38  5043.9 1062.15  5065.4 1063.46  5072.2 1064.88  5093.8 1065.64
  5100.6 1067.27  5114.8 1067.52  5164.1 1072.16  5348.3  1076.5  5489.8 1078.37
#Mann= 3 ,-1 , 0
  4496.8     .05       0  4993.6     .05       0  5003.4     .05       0
Bank Sta=4993.6,5003.4
XS Rating Curve= 0 ,0
Exp/Cntr=0.3,0.1

Type RM Length L Ch R = 1 ,5414    ,455,455,455
BEGIN DESCRIPTION:
CEDAR HOLLOW CREEK 12.0
END DESCRIPTION:
XS GIS Cut Line= 3
      2848405.72     10275803.08      2848311.25       10275889.
       2848105.7     10276253.08
#Sta/Elev= 30
  4872.3 1075.07  4879.4 1074.66  4886.2 1072.38  4893.6 1071.45  4900.4 1069.86
  4910.5 1066.32  4914.6 1064.51    4920 1063.34  4928.8  1062.6  4936.2 1064.38
  4950.4 1062.22  4957.2 1060.35  4978.8 1058.74  4987.9 1055.29  4988.4 1054.79
  4997.6 1054.79  4998.1 1055.29  5006.2 1055.97  5021.7 1057.75  5037.6  1061.4
  5043.4 1061.37  5050.7 1062.66  5059.3 1063.12  5205.1 1065.51  5259.7 1067.45
  5307.6 1070.04  5323.6 1070.46  5329.3 1070.11  5337.7 1070.71  5418.1 1072.44
#Mann= 7 ,-1 , 0
  4872.3     .05       0  4910.5     .12       0    4920     .05       0
  4987.9     .05       0  4998.1     .05       0  5006.2     .12       0
  5259.7     .05       0
Bank Sta=4987.9,4998.1
XS Rating Curve= 0 ,0
Exp/Cntr=0.3,0.1

Type RM Length L Ch R = 1 ,4959    ,313,313,313
BEGIN DESCRIPTION:
CEDAR HOLLOW CREEK 11.0
END DESCRIPTION:
XS GIS Cut Line= 3
      2848005.68     10275603.13       2847872.5       10275914.
      2847905.68      10276053.1
#Sta/Elev= 30
  4661.8 1076.76  4676.3 1075.55  4683.5 1073.94  4723.4 1069.53  4728.9 1069.83
    4747 1068.03  4770.6 1066.92  4781.5 1065.47  4799.6 1065.29  4817.2 1063.42
  4823.2    1063  4828.6 1063.76  4835.8 1062.45  4852.2  1061.3  4899.4 1060.56
  4928.4 1058.72  4951.9 1059.46  4957.4 1060.54  4966.4  1056.8    4981 1053.42
  4990.8 1052.04  4991.6 1052.03  4992.1 1051.53  5001.4 1051.53  5001.9 1052.03
  5035.2 1061.11  5040.3 1063.77  5060.8 1064.96  5082.4 1064.63    5143 1067.84
#Mann= 5 ,-1 , 0
  4661.8     .05       0  4817.2     .12       0  4990.8     .05       0
  4991.6     .03       0  5001.9     .05       0
Bank Sta=4991.6,5001.9
XS Rating Curve= 0 ,0
Exp/Cntr=0.3,0.1

Type RM Length L Ch R = 1 ,4646    ,540,540,540
BEGIN DESCRIPTION:
CEDAR HOLLOW CREEK 10.0
END DESCRIPTION:
XS GIS Cut Line= 3
      2847805.66     10275553.13      2847487.62      10275865.1
      2847172.15     10276579.44
#Sta/Elev= 30
  4727.7 1071.12  4741.7 1070.72  4777.2 1065.14  4812.5 1061.49  4840.8 1059.57
  4876.2 1057.91  4925.6 1057.56    4961 1055.44  4975.2 1053.87  4991.2 1049.23
  4991.7 1048.73  5001.5 1049.23  5010.5 1051.73  5031.8 1060.25  5038.8 1062.06
  5052.9 1063.81  5095.3 1064.07  5130.8  1063.2  5198.8 1063.69  5212.2  1064.5
    5241 1063.87  5264.3  1065.7  5316.4 1065.19    5363 1066.11  5438.4 1065.95
  5520.8 1066.96  5619.2 1066.75    5652 1065.98  5664.6 1066.76  5954.1 1073.05
#Mann= 4 ,-1 , 0
  4727.7     .12       0  4991.2     .07       0  5001.5     .12       0
  5198.8     .05       0
Bank Sta=4991.2,5001.5
XS Rating Curve= 0 ,0
Exp/Cntr=0.3,0.1

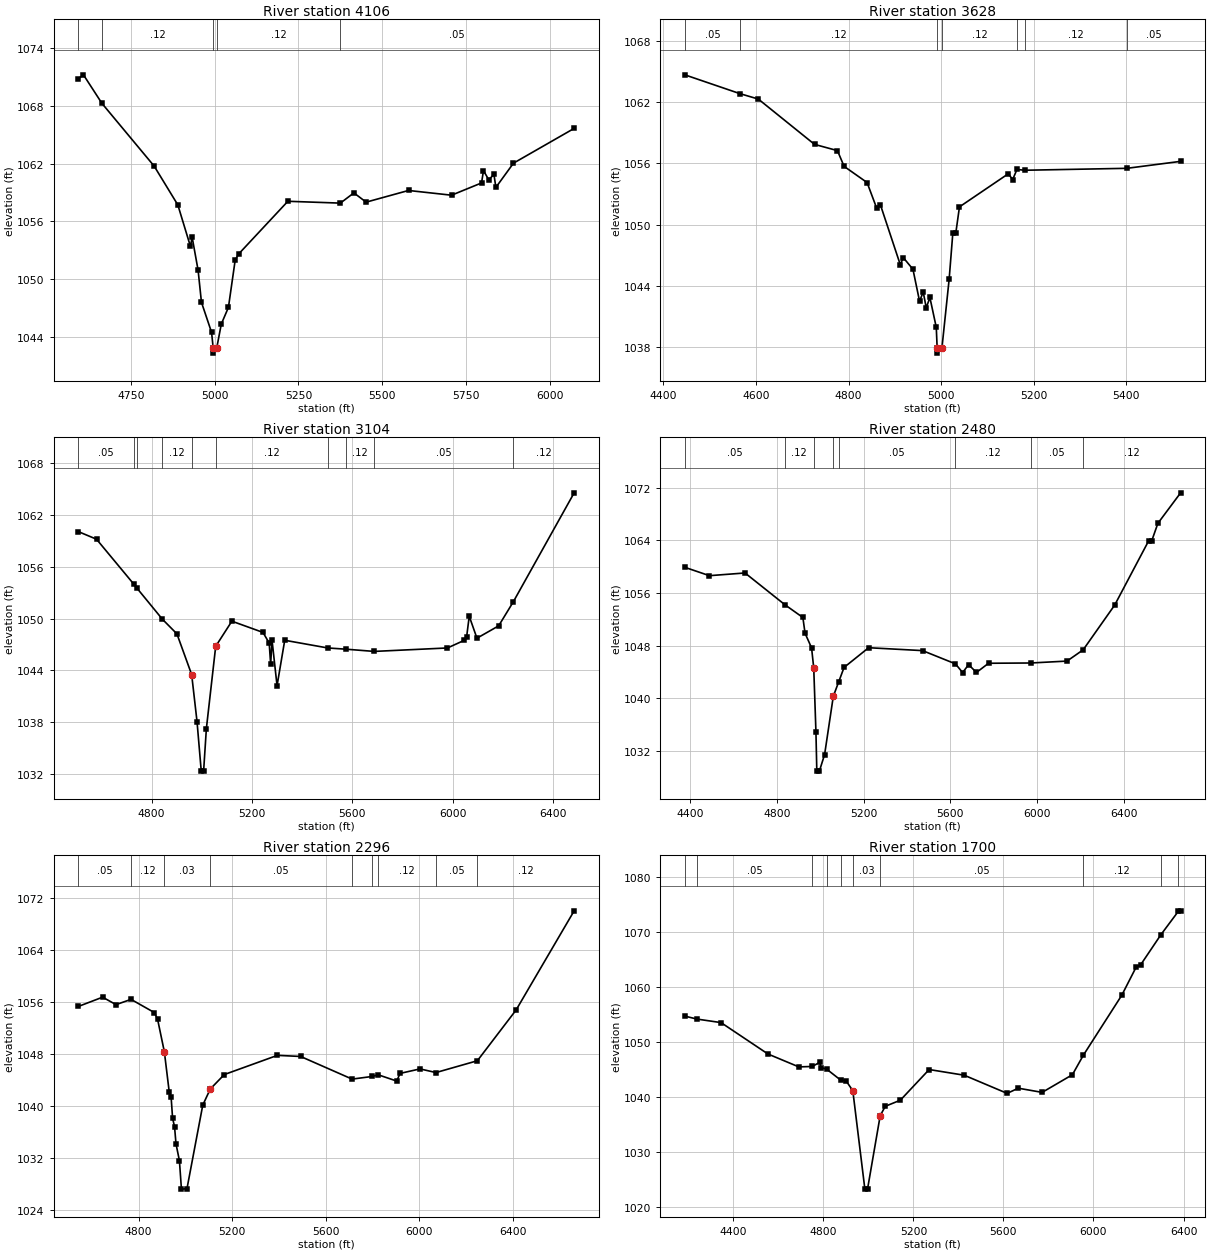
Type RM Length L Ch R = 1 ,4106    ,478,478,478
BEGIN DESCRIPTION:
CEDAR HOLLOW CREEK 9.0
END DESCRIPTION:
XS GIS Cut Line= 3
       2847850.9      10275222.1      2847289.01     10275282.51
      2846820.04     10276067.11
#Sta/Elev= 30
  4593.2 1070.79  4608.5 1071.19  4663.7 1068.23  4819.7 1061.72  4890.1 1057.71
  4927.7 1053.41  4932.7 1054.37  4950.5 1050.95  4960.5 1047.63  4990.7 1044.51
  4995.6 1042.86  4996.1 1042.36  5005.9 1042.86  5019.7 1045.37    5041  1047.1
  5061.1 1051.99  5071.2 1052.62  5218.3 1058.09  5374.9  1057.9  5415.3 1058.96
  5451.8    1058  5578.2 1059.21  5706.6 1058.72  5796.1 1059.99  5801.9 1061.27
  5817.5 1060.32  5833.1 1060.87  5838.9 1059.53  5891.4 1062.04  6072.4 1065.64
#Mann= 5 ,-1 , 0
  4593.2     .05       0  4663.7     .12       0  4995.6     .07       0
  5005.9     .12       0  5374.9     .05       0
Bank Sta=4995.6,5005.9
XS Rating Curve= 0 ,0
Exp/Cntr=0.3,0.1

Type RM Length L Ch R = 1 ,3628    ,524,524,524
BEGIN DESCRIPTION:
CEDAR HOLLOW CREEK 8.0
END DESCRIPTION:
XS GIS Cut Line= 3
      2847578.42     10274571.86      2847145.88     10275103.27
      2846950.32     10275435.84
#Sta/Elev= 30
  4446.4 1064.65  4565.5 1062.81  4605.2 1062.28  4726.6 1057.85  4776.1 1057.24
  4790.5  1055.7  4840.1 1054.12  4860.9 1051.61  4868.8 1051.96  4911.9 1046.08
  4918.3 1046.78  4939.2 1045.64  4953.5 1042.51  4961.4 1043.42  4967.9 1041.87
  4975.8 1042.88  4989.6 1039.96  4991.5 1037.94    4992 1037.44  5001.8 1037.94
  5017.4 1044.66  5025.4 1049.21  5031.8 1049.19  5039.7 1051.74  5145.3 1054.98
  5154.6 1054.41  5163.9  1055.4  5180.3 1055.32  5401.5 1055.51  5517.4 1056.19
#Mann= 7 ,-1 , 0
  4446.4     .05       0  4565.5     .12       0  4991.5     .07       0
  5001.8     .12       0  5163.9     .05       0  5180.3     .12       0
  5401.5     .05       0
Bank Sta=4991.5,5001.8
XS Rating Curve= 0 ,0
Exp/Cntr=0.3,0.1

Type RM Length L Ch R = 1 ,3104    ,624,624,624
BEGIN DESCRIPTION:
CEDAR HOLLOW CREEK 7.0
END DESCRIPTION:
XS GIS Cut Line= 3
      2847058.94     10274288.52      2846730.95     10274847.92
      2845482.77     10275298.24
#Sta/Elev= 30
  4508.1 1060.06  4580.5 1059.18    4729 1053.98    4742  1053.5  4842.9 1049.92
  4900.9 1048.22  4959.6 1043.51    4981 1038.06  4997.8 1032.33  5007.2 1032.33
  5018.2 1037.25  5055.4 1046.78  5119.8 1049.69  5243.7 1048.39  5268.5 1047.16
  5274.4 1044.69  5279.7 1047.52  5299.8 1042.22  5330.4 1047.48  5501.6 1046.59
  5573.1 1046.45  5686.9 1046.19  5978.8 1046.59  6045.5 1047.47  6055.2  1047.9
  6065.5 1050.26  6096.2 1047.72  6182.7 1049.15  6241.4 1051.95  6483.5 1064.55
#Mann= 10 ,-1 , 0
  4508.1     .05       0    4729     .12       0    4742     .05       0
  4842.9     .12       0  4959.6     .07       0  5055.4     .12       0
  5501.6     .05       0  5573.1     .12       0  5686.9     .05       0
  6241.4     .12       0
Bank Sta=4959.6,5055.4
XS Rating Curve= 0 ,0
Exp/Cntr=0.3,0.1

Type RM Length L Ch R = 1 ,2480    ,184,184,184
BEGIN DESCRIPTION:
CEDAR HOLLOW CREEK 6.0
END DESCRIPTION:
XS GIS Cut Line= 3
      2847318.96     10274203.99      2846603.49     10274266.51
      2845389.32     10275264.53
#Sta/Elev= 30
  4373.9 1059.91  4487.6 1058.64  4652.1 1059.05  4836.1 1054.23  4919.2 1052.29
  4929.3 1049.89  4959.4 1047.68  4969.4 1044.61  4979.5 1034.96  4983.6 1028.96
  4995.4 1028.96  5019.6 1031.48  5059.8 1040.33  5084.6 1042.51  5109.5 1044.71
  5222.9  1047.7  5471.9 1047.26  5623.8 1045.25    5657 1043.93  5684.7 1045.13
  5720.8 1043.94  5776.8 1045.34  5971.3 1045.38  6139.1 1045.67  6213.7 1047.38
  6359.4 1054.18  6515.8 1063.91  6530.1 1063.91  6558.8 1066.59  6663.8 1071.22
#Mann= 8 ,-1 , 0
  4373.9     .05       0  4836.1     .12       0  4969.4     .07       0
  5059.8     .12       0  5084.6     .05       0  5623.8     .12       0
  5971.3     .05       0  6213.7     .12       0
Bank Sta=4969.4,5059.8
XS Rating Curve= 0 ,0
Exp/Cntr=0.3,0.1

Type RM Length L Ch R = 1 ,2296    ,596,596,596
BEGIN DESCRIPTION:
CEDAR HOLLOW CREEK 5.0
END DESCRIPTION:
XS GIS Cut Line= 3
      2846913.63     10273725.44      2846570.24     10274173.11
      2845405.69     10275203.11
#Sta/Elev= 30
  4542.4 1055.35  4646.2 1056.78  4703.3 1055.63  4767.7 1056.44  4867.1 1054.41
    4881 1053.39    4910 1048.36  4930.8 1042.18    4939 1041.32  4945.3 1038.09
  4953.5 1036.84  4959.8 1034.16  4974.4 1031.58    4983 1027.19 5006.67 1027.26
  5074.1 1040.13  5106.2 1042.62  5166.1 1044.85    5393 1047.81  5492.3 1047.64
  5712.4 1044.15  5798.9 1044.56  5823.3 1044.82    5903 1043.85  5917.3 1045.03
  6002.6 1045.72  6070.8 1045.16  6247.6 1046.98  6413.3 1054.81  6661.3 1070.09
#Mann= 9 ,-1 , 0
  4542.4     .05       0  4767.7     .12       0    4910     .03       0
  5106.2     .05       0  5712.4     .12       0  5798.9     .05       0
  5823.3     .12       0  6070.8     .05       0  6247.6     .12       0
Bank Sta=4910,5106.2
XS Rating Curve= 0 ,0
Exp/Cntr=0.3,0.1

Type RM Length L Ch R = 1 ,1700    ,660,660,660
BEGIN DESCRIPTION:
CEDAR HOLLOW CREEK 4.0
END DESCRIPTION:
XS GIS Cut Line= 4
      2846692.04     10273365.79      2846158.04     10273736.32
      2846007.58     10274046.57       2845155.7      10274903.1
#Sta/Elev= 30
  4184.4 1054.74  4238.4  1054.2  4345.3 1053.56    4554 1047.85  4691.1 1045.51
  4750.8 1045.59  4783.7 1046.34  4789.8 1045.39  4814.4 1045.11  4877.9 1043.08
    4900 1043.03  4930.8 1041.19  4984.4  1023.3  4996.2  1023.3  5052.5 1036.65
  5075.1 1038.35    5142 1039.46    5270 1045.03  5425.6    1044  5616.5  1040.7
    5666 1041.64    5772 1040.88  5906.4 1044.09    5955 1047.63  6125.6 1058.52
  6189.2 1063.61  6210.4 1064.11  6300.1 1069.56  6377.5 1073.81  6387.2 1073.87
#Mann= 10 ,-1 , 0
  4184.4     .12       0  4238.4     .05       0  4750.8     .12       0
  4814.4     .05       0  4877.9     .12       0  4930.8     .03       0
  5052.5     .05       0    5955     .12       0  6300.1     .05       0
  6377.5     .12       0
Bank Sta=4930.8,5052.5
XS Rating Curve= 0 ,0
Exp/Cntr=0.3,0.1

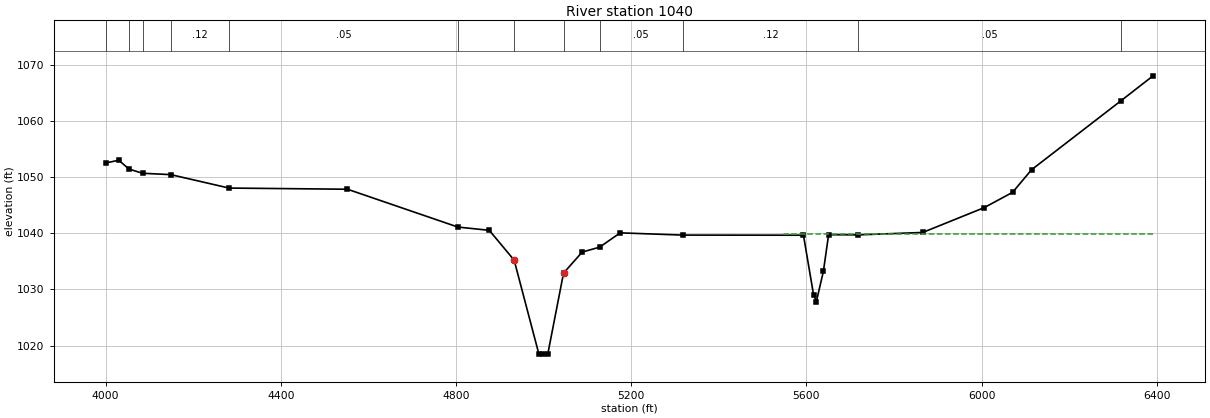
Type RM Length L Ch R = 1 ,1040    ,896,896,896
BEGIN DESCRIPTION:
Mapping XS 770ea202
END DESCRIPTION:
XS GIS Cut Line= 4
      2846663.03     10272962.53      2845955.95     10273337.34
      2845712.02     10273560.93      2845093.91     10274658.58
#Sta/Elev= 30
  4000.6 1052.49  4029.9 1052.97  4053.4  1051.4  4084.3 1050.65  4148.6 1050.41
  4281.8 1048.02  4552.2 1047.81  4804.3 1041.08  4875.9  1040.5  4932.7  1035.2
    4989 1018.54  4997.6 1018.47  5009.5 1018.47  5045.5 1032.89  5088.1 1036.63
  5127.8  1037.5  5174.9 1040.05  5317.8 1039.65  5593.3 1039.63  5616.3 1029.06
  5622.8 1027.83  5638.8  1033.2  5650.7 1039.72  5718.7 1039.69  5865.6 1040.12
  6005.8 1044.53  6070.8 1047.26  6114.1 1051.28  6317.9 1063.53  6391.5 1067.99
#Mann= 12 ,-1 , 0
  4000.6     .05       0  4053.4     .12       0  4084.3     .05       0
  4148.6     .12       0  4281.8     .05       0  4804.3     .12       0
  4932.7     .03       0  5045.5     .12       0  5127.8     .05       0
  5317.8     .12       0  5718.7     .05       0  6317.9     .12       0
#XS Ineff= 2 , 0
                         5549.75         1039.78
Permanent Ineff=
       F       F
Bank Sta=4932.7,5045.5
XS Rating Curve= 0 ,0
Exp/Cntr=0.3,0.1