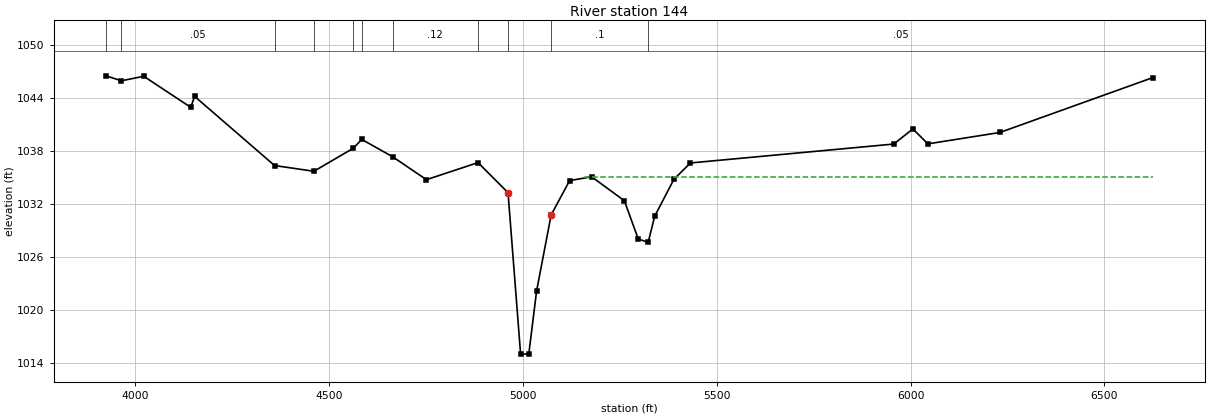
HEC-RAS study CEDAR HOLLOW CREEK.prj: CEDAR HOLLOW CREEK Base Level Engineering

--- CEDAR HOLLOW CREEK.g01 (geometry) --- (continued)

Type RM Length L Ch R = 1 ,144     ,0,0,0
BEGIN DESCRIPTION:
CEDAR HOLLOW CREEK 2.0
END DESCRIPTION:
XS GIS Cut Line= 4
       2846470.5     10272450.32      2845645.83     10272610.17
      2845112.19     10273089.55      2844581.43     10274103.24
#Sta/Elev= 30
  3923.7 1046.52  3963.9 1045.96  4021.3 1046.47  4142.5 1042.96  4152.7 1044.19
  4358.8 1036.37  4460.3 1035.72  4561.8 1038.32  4583.9 1039.32  4663.2 1037.37
  4750.7 1034.77  4883.7  1036.7 4961.16  1033.3  4993.6 1015.04  5014.7 1015.03
 5034.84 1022.17  5072.4 1030.78    5120 1034.66  5176.8  1035.1  5261.3 1032.39
  5297.1 1028.06  5322.7 1027.68  5339.7 1030.65  5389.1 1034.81  5431.7 1036.66
  5956.1  1038.8  6005.8 1040.51  6044.3 1038.82  6230.1 1040.11  6625.3 1046.33
#Mann= 11 ,-1 , 0
  3923.7     .12       0  3963.9     .05       0  4358.8     .12       0
  4460.3     .05       0  4561.8     .12       0  4583.9     .05       0
  4663.2     .12       0  4883.7      .1       0 4961.16     .03       0
  5072.4      .1       0  5322.7     .05       0
#XS Ineff= 2 , 0
                         5160.71         1035.09
Permanent Ineff=
       F       F
Bank Sta=4961.16,5072.4
XS Rating Curve= 0 ,0
Exp/Cntr=0.3,0.1

Chan Stop Cuts=-1
Use User Specified Reach Order=0
Composite Channel Slope=5