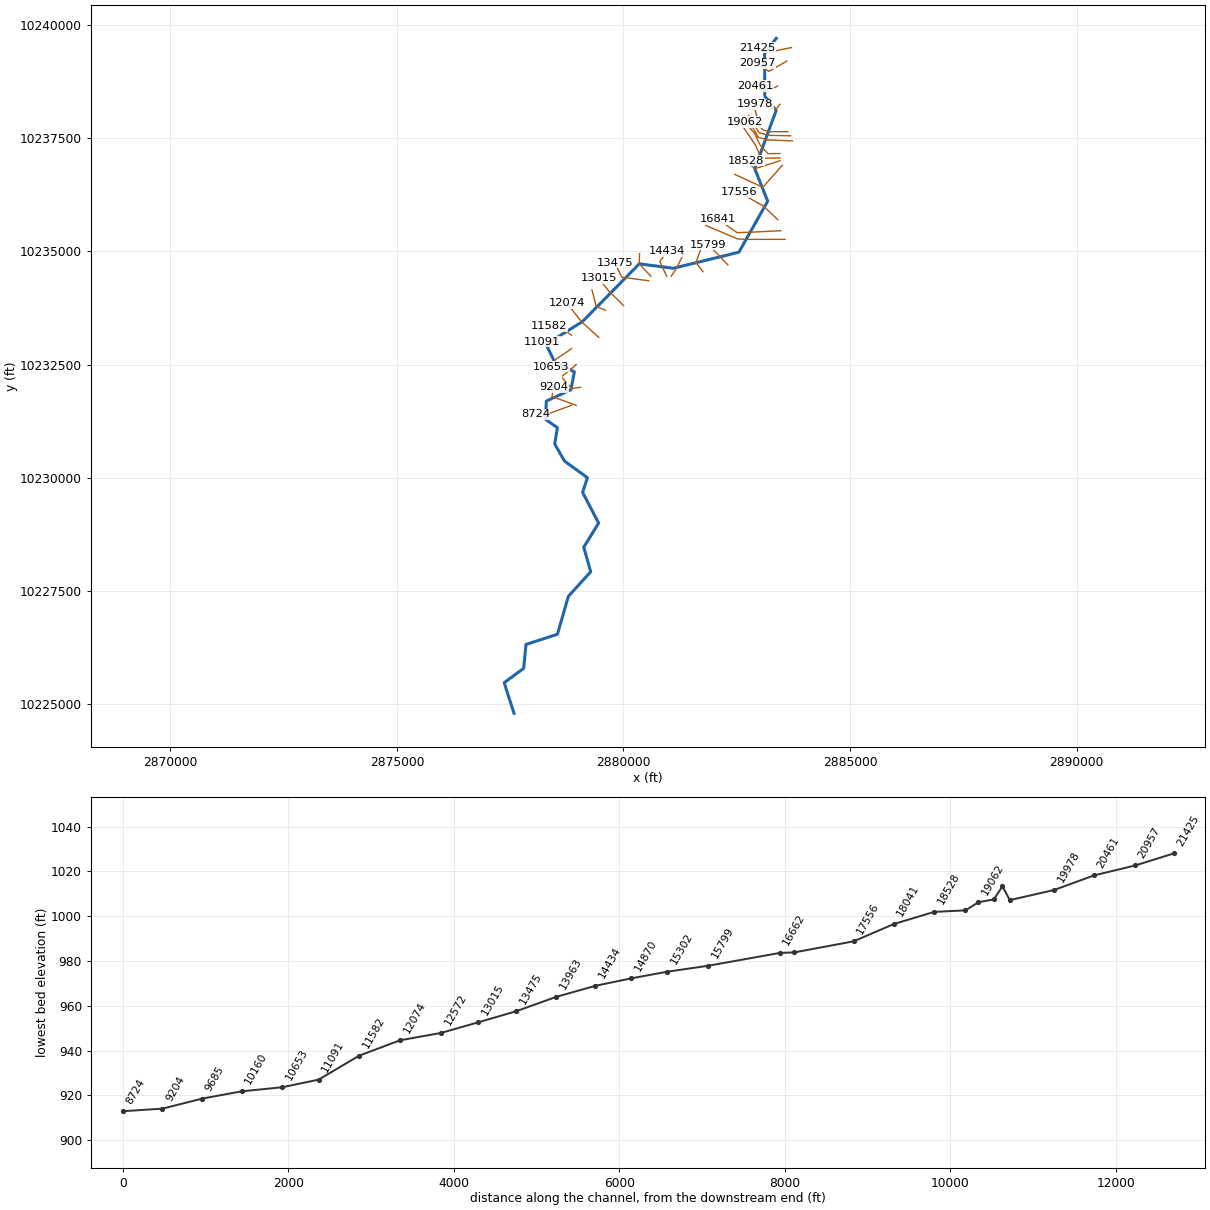
--- FRENCH JOHN CREEK.prj (project) ---

Proj Title=FRENCH JOHN CREEK Base Level Engineering
Current Plan=p01
Default Exp/Contr=0.3,0.1
English Units
Geom File=g01
Flow File=f01
Plan File=p01
BEGIN DESCRIPTION:
FRENCH JOHN CREEK
END DESCRIPTION:

--- FRENCH JOHN CREEK.p01 (plan) ---

Plan Title=Multiple Run
Short Identifier=Multiple
Geom File=g01
Flow File=f01
Subcritical Flow
K Sum by GR= 0
Std Step Tol= 0.01
Critical Tol= 0.01
Num of Std Step Trials= 20
Max Error Tol= 0.3
Flow Tol Ratio= 0.001
Split Flow NTrial= 30
Split Flow Tol= 0.02
Split Flow Ratio= 0.02
Log Output Level= 0
Friction Slope Method= 1
Unsteady Friction Slope Method= 2
Unsteady Bridges Friction Slope Method= 1
Parabolic Critical Depth
Global Vel Dist=  1 , 1 , 1
Global Log Level= 0
CheckData=True
Encroach Param= -1, 0, 0, 0
BEGIN DESCRIPTION:
Multiple Run
END DESCRIPTION:

--- FRENCH JOHN CREEK.f01 (steady flow) ---

Flow Title=Multiple
Number of Profiles=7
Profile Names=10-year,25-year,50-year,1pct_min,100-year,1pct_plu,500-year
River Rch & RM= FRENCH JOHN CREE,Reach-1,21425
     449     729     836     601    1096    1998    1479
River Rch & RM= FRENCH JOHN CREE,Reach-1,12572
     763    1293    1511    1008    2026    4070    2751
River Rch & RM= FRENCH JOHN CREE,Reach-1,3442
     882    1512    1760    1148    2372    4900    3226
Boundary for River Rch & Prof#=FRENCH JOHN CREE,Reach-1,1
Up Type=0
Dn Type=3
Dn Slope=0.005
Boundary for River Rch & Prof#=FRENCH JOHN CREE,Reach-1,2
Up Type=0
Dn Type=3
Dn Slope=0.005
Boundary for River Rch & Prof#=FRENCH JOHN CREE,Reach-1,3
Up Type=0
Dn Type=3
Dn Slope=0.005
Boundary for River Rch & Prof#=FRENCH JOHN CREE,Reach-1,4
Up Type=0
Dn Type=3
Dn Slope=0.005
Boundary for River Rch & Prof#=FRENCH JOHN CREE,Reach-1,5
Up Type=0
Dn Type=3
Dn Slope=0.005
Boundary for River Rch & Prof#=FRENCH JOHN CREE,Reach-1,6
Up Type=0
Dn Type=3
Dn Slope=0.005
Boundary for River Rch & Prof#=FRENCH JOHN CREE,Reach-1,7
Up Type=0
Dn Type=3
Dn Slope=0.005

--- FRENCH JOHN CREEK.g01 (geometry) ---

Geom Title=Existing Conditions

River Reach=FRENCH JOHN CREE,Reach-1
Reach XY= 30
      2883373.00     10239707.00      2883115.50     10239383.00
      2883120.50     10238427.00      2883369.75     10238113.00
      2882898.00     10236828.00      2883184.00     10236111.00
      2882547.75     10234984.00      2881100.25     10234629.00
      2880349.00     10234727.00      2879096.00     10233452.00
      2878292.25     10232949.00      2878499.00     10232524.00
      2878917.75     10232343.00      2878839.75     10231946.00
      2878299.00     10231696.00      2878277.25     10231296.00
      2878542.75     10231108.00      2878483.50     10230749.00
      2878699.00     10230371.00      2879205.25     10230005.00
      2879099.00     10229680.00      2879452.25     10229002.00
      2879124.00     10228468.00      2879277.25     10227927.00
      2878784.50     10227383.00      2878542.75     10226546.00
      2877849.00     10226321.00      2877797.75     10225794.00
      2877367.75     10225477.00      2877585.25     10224799.00

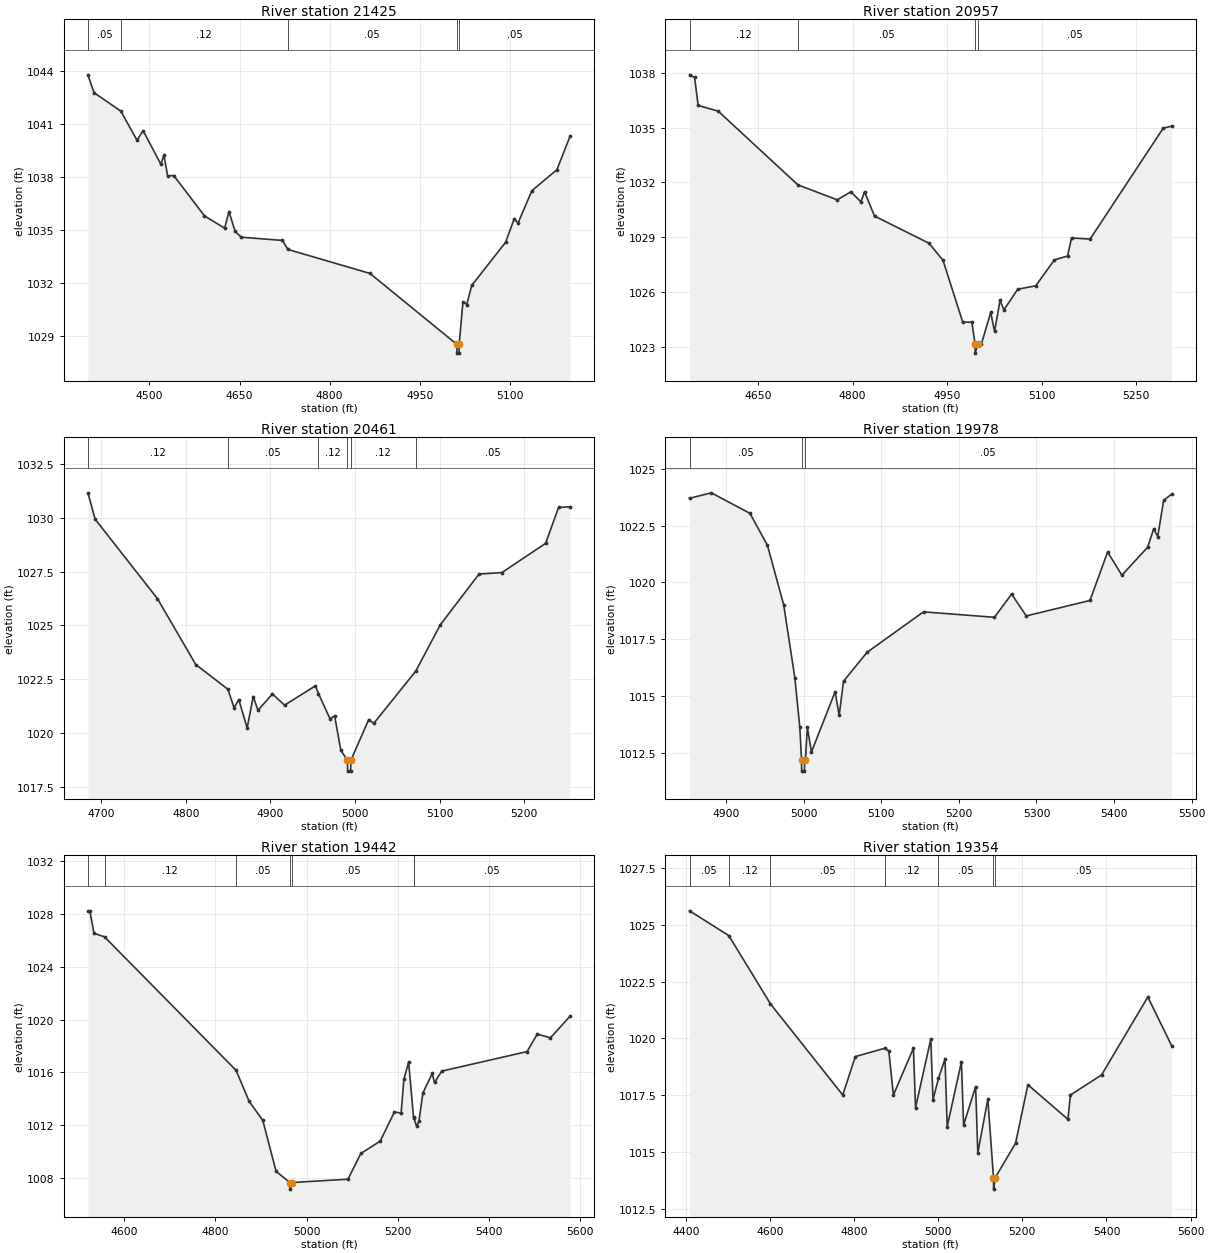
Type RM Length L Ch R = 1,21425,468,468,468
BEGIN DESCRIPTION:
FRENCH JOHN CREEK 44.0
END DESCRIPTION:
XS GIS Cut Line= 3
      2883705.70     10239503.12      2883115.50     10239383.00
      2882955.70     10239503.10
#Sta/Elev= 30
  4397.7 1043.78  4407.9 1042.77  4452.4 1041.73  4479.4 1040.08  4489.6 1040.62
  4519.1 1038.72  4524.2 1039.24  4530.4 1038.06  4540.6 1038.08  4591.6 1035.80
  4625.3 1035.10  4632.4 1036.04  4642.6 1034.93  4652.8 1034.59  4721.4 1034.41
  4730.4 1033.90  4867.1 1032.54  5011.5 1028.53  5011.8 1028.03  5015.3 1028.03
  5015.5 1028.53  5021.8 1030.94  5028.1 1030.78  5036.4 1031.86  5092.7 1034.30
  5107.2 1035.64  5113.5 1035.39  5136.4 1037.22  5178.1 1038.41  5199.9 1040.29
#Mann=5,-1,0
  4397.7    0.05       0  4452.4    0.12       0  4730.4    0.05       0
  5011.5    0.05       0  5015.5    0.05       0
Bank Sta=5011.5,5015.5
Exp/Cntr=0.3,0.1

Type RM Length L Ch R = 1,20957,496,496,496
BEGIN DESCRIPTION:
FRENCH JOHN CREEK 43.0
END DESCRIPTION:
XS GIS Cut Line= 3
      2883605.71     10239203.12      2883206.50     10238977.00
      2882955.66     10239153.13
#Sta/Elev= 30
  4541.2 1037.89  4549.2 1037.75  4554.9 1036.21  4586.7 1035.90  4713.2 1031.86
  4775.7 1031.04  4797.3 1031.48  4813.2 1030.93  4819.0 1031.48  4834.9 1030.15
  4921.4 1028.66  4943.5 1027.73  4974.8 1024.35  4989.4 1024.33  4994.5 1023.14
  4994.7 1022.64  4998.5 1023.14  5004.5 1023.14  5019.3 1024.87  5025.4 1023.83
  5034.1 1025.53  5040.3 1025.01  5062.1 1026.14  5090.8 1026.33  5120.4 1027.75
  5141.3 1027.96  5147.6 1028.95  5177.1 1028.89  5293.0 1034.96  5306.5 1035.08
#Mann=4,-1,0
  4541.2    0.12       0  4713.2    0.05       0  4994.5    0.05       0
  4998.5    0.05       0
Bank Sta=4994.5,4998.5
Exp/Cntr=0.3,0.1

Type RM Length L Ch R = 1,20461,483,483,483
BEGIN DESCRIPTION:
FRENCH JOHN CREEK 42.0
END DESCRIPTION:
XS GIS Cut Line= 3
      2883405.68     10238653.11      2883120.50     10238517.00
      2882905.69     10238653.11
#Sta/Elev= 30
  4684.0 1031.17  4692.6 1029.94  4766.2 1026.25  4811.6 1023.18  4849.6 1022.03
  4856.9 1021.17  4862.5 1021.55  4872.4 1020.23  4879.6 1021.69  4885.2 1021.05
  4902.3 1021.81  4916.7 1021.29  4953.2 1022.19  4956.8 1021.82  4970.4 1020.66
  4975.9 1020.79  4983.2 1019.19  4991.1 1018.72  4991.3 1018.22  4994.8 1018.22
  4995.1 1018.72  5016.2 1020.62  5022.1 1020.44  5071.8 1022.87  5100.9 1025.03
  5146.7 1027.39  5173.8 1027.46  5225.5 1028.82  5240.8 1030.49  5254.3 1030.52
#Mann=6,-1,0
  4684.0    0.12       0  4849.6    0.05       0  4956.8    0.12       0
  4991.1    0.07       0  4995.1    0.12       0  5071.8    0.05       0
Bank Sta=4991.1,4995.1
Exp/Cntr=0.3,0.1

Type RM Length L Ch R = 1,19978,536,536,536
BEGIN DESCRIPTION:
FRENCH JOHN CREEK 41.0
END DESCRIPTION:
XS GIS Cut Line= 3
      2883455.67     10238253.10      2883365.50     10238137.00
      2882905.73     10238253.10
#Sta/Elev= 30
  4853.0 1023.70  4881.0 1023.94  4930.8 1023.04  4953.4 1021.63  4974.3 1019.02
  4988.7 1015.81  4995.1 1013.63  4997.3 1012.21  4997.5 1011.71  5001.0 1011.71
  5001.3 1012.21  5002.3 1012.21  5004.8 1013.63  5010.1 1012.55  5040.6 1015.20
  5045.8 1014.16  5051.4 1015.66  5081.7 1016.93  5154.5 1018.71  5245.9 1018.47
  5268.0 1019.49  5286.9 1018.53  5369.0 1019.21  5391.7 1021.34  5410.1 1020.32
  5443.3 1021.55  5451.1 1022.36  5456.3 1022.02  5463.9 1023.61  5474.2 1023.88
#Mann=3,-1,0
  4853.0    0.05       0  4997.3    0.05       0  5001.3    0.05       0
Bank Sta=4997.3,5001.3
Exp/Cntr=0.3,0.1

Type RM Length L Ch R = 1,19442,88,88,88
BEGIN DESCRIPTION:
Mapping XS a95969c9
END DESCRIPTION:
XS GIS Cut Line= 5
      2883629.06     10237645.79      2883212.44     10237645.79
      2883082.23     10237684.85      2883008.44     10237758.64
      2882900.30     10238143.63
#Sta/Elev= 30
  4520.5 1028.23  4524.7 1028.23  4533.9 1026.53  4556.9 1026.26  4845.3 1016.16
  4873.9 1013.82  4903.9 1012.37  4933.0 1008.52  4963.1 1007.67  4963.3 1007.17
  4967.1 1007.67  5090.6 1007.92  5118.9 1009.87  5161.3 1010.80  5192.4 1013.01
  5207.1 1012.92  5213.2 1015.48  5223.6 1016.79  5234.3 1012.64  5234.9 1012.58
  5241.1 1011.92  5246.3 1012.33  5254.8 1014.44  5275.2 1015.92  5280.4 1015.24
  5296.3 1016.10  5483.3 1017.58  5505.6 1018.90  5534.5 1018.62  5577.3 1020.25
#Mann=7,-1,0
  4520.5    0.05       0  4556.9    0.12       0  4845.3    0.05       0
  4963.1    0.03       0  4967.1    0.05       0  5234.3    0.12       0
  5234.9    0.05       0
Bank Sta=4963.1,4967.1
Exp/Cntr=0.3,0.1

Type RM Length L Ch R = 1,19354,104,104,104
BEGIN DESCRIPTION:
Mapping XS 9fef4f42
END DESCRIPTION:
XS GIS Cut Line= 6
      2883689.88     10237554.64      2883238.48     10237563.32
      2883142.99     10237580.68      2883051.85     10237606.73
      2882991.08     10237624.09      2882765.40     10238001.66
#Sta/Elev= 30
  4408.6 1025.61  4502.0 1024.52  4600.9 1021.52  4772.9 1017.51  4802.9 1019.20
  4873.7 1019.57  4882.5 1019.44  4893.4 1017.51  4941.0 1019.57  4946.0 1016.95
  4982.3 1019.97  4987.5 1017.30  5000.6 1018.24  5016.1 1019.09  5021.3 1016.12
  5055.1 1018.97  5060.3 1016.19  5088.9 1017.88  5094.1 1014.96  5117.9 1017.33
  5131.4 1013.87  5131.7 1013.37  5135.4 1013.87  5183.9 1015.39  5213.2 1017.96
  5308.5 1016.44  5314.3 1017.51  5388.3 1018.39  5498.4 1021.82  5555.0 1019.68
#Mann=7,-1,0
  4408.6    0.05       0  4502.0    0.12       0  4600.9    0.05       0
  4873.7    0.12       0  5000.6    0.05       0  5131.4    0.07       0
  5135.4    0.05       0
Bank Sta=5131.4,5135.4
Exp/Cntr=0.3,0.1

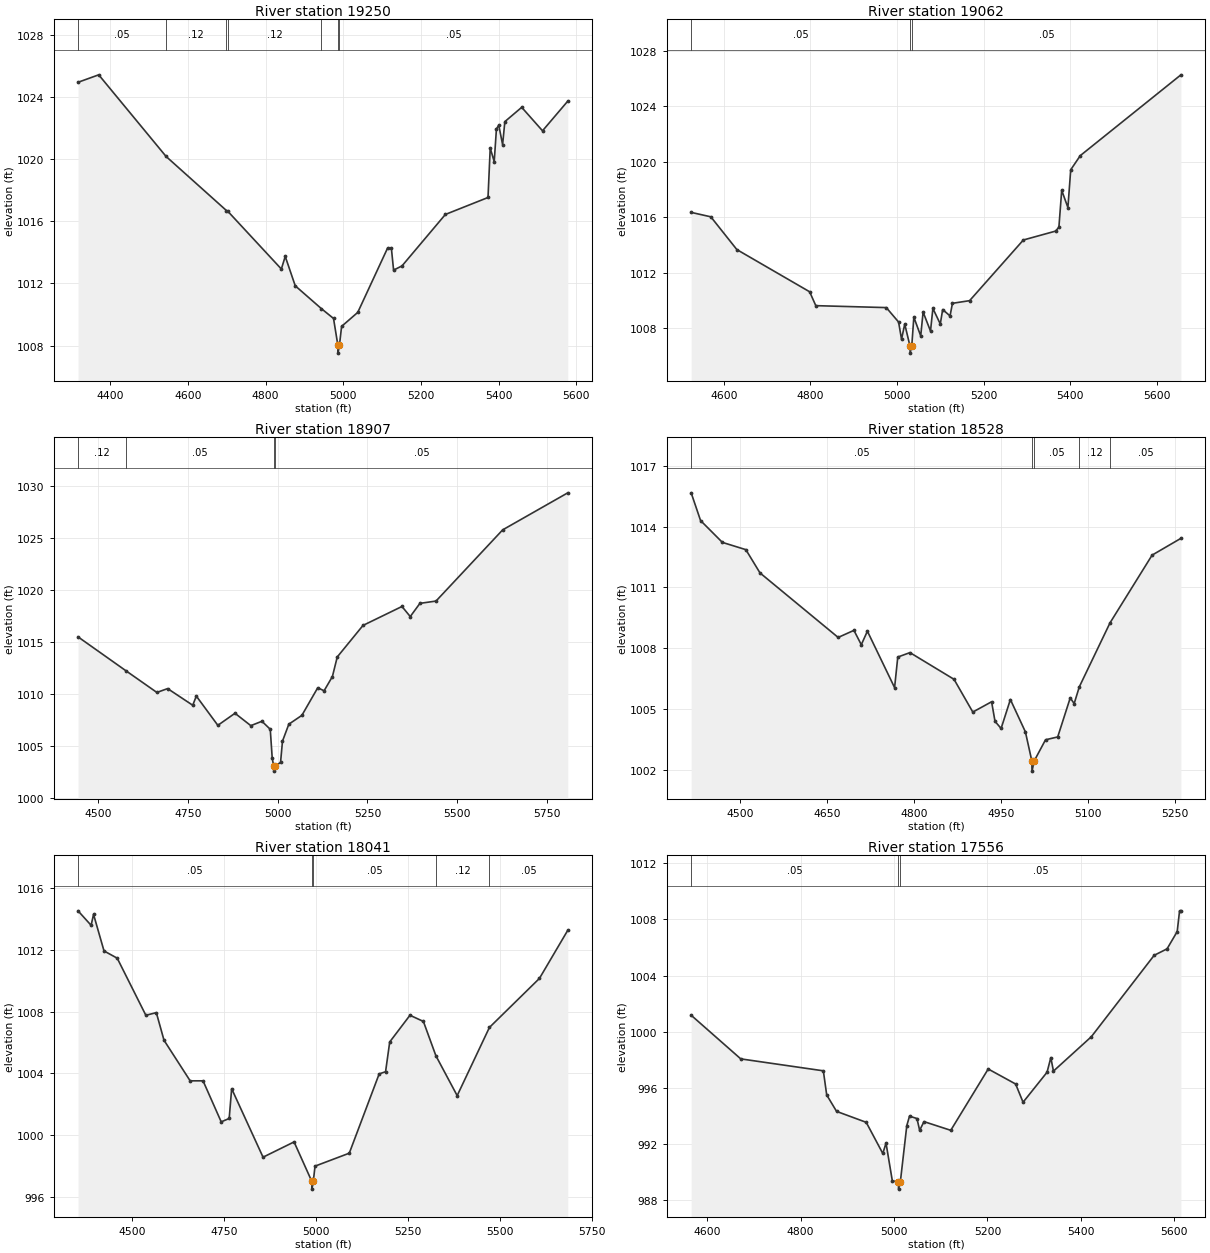
Type RM Length L Ch R = 1,19250,188,188,188
BEGIN DESCRIPTION:
Mapping XS deda96a9
END DESCRIPTION:
XS GIS Cut Line= 4
      2883728.92     10237441.80      2883186.39     10237463.50
      2882973.72     10237524.26      2882730.71     10237958.21
#Sta/Elev= 30
  4316.9 1024.93  4370.2 1025.41  4543.7 1020.16  4699.2 1016.68  4702.8 1016.63
  4840.6 1012.92  4850.6 1013.73  4876.4 1011.84  4943.8 1010.37  4975.0 1009.74
  4986.2 1008.01  4986.5 1007.51  4990.2 1008.01  4995.8 1009.23  5037.4 1010.13
  5114.1 1014.26  5124.0 1014.26  5129.7 1012.85  5151.4 1013.12  5263.1 1016.43
  5372.9 1017.52  5378.6 1020.70  5388.9 1019.83  5394.6 1021.93  5400.6 1022.17
  5410.5 1020.92  5416.3 1022.40  5459.7 1023.32  5513.3 1021.81  5578.4 1023.72
#Mann=7,-1,0
  4316.9    0.05       0  4543.7    0.12       0  4699.2    0.05       0
  4702.8    0.12       0  4943.8    0.05       0  4986.2    0.03       0
  4990.2    0.05       0
Bank Sta=4986.2,4990.2
Exp/Cntr=0.3,0.1

Type RM Length L Ch R = 1,19062,155,155,155
BEGIN DESCRIPTION:
Mapping XS 52e9b211
END DESCRIPTION:
XS GIS Cut Line= 5
      2883451.12     10237164.02      2883190.73     10237159.68
      2883017.12     10237350.65      2882891.26     10237611.07
      2882683.04     10237858.32
#Sta/Elev= 30
  4524.6 1016.35  4570.0 1016.03  4630.1 1013.67  4798.2 1010.63  4812.4 1009.63
  4975.2 1009.49  5003.6 1008.45  5010.4 1007.21  5017.8 1008.30  5030.0 1006.71
  5030.2 1006.21  5034.0 1006.71  5038.8 1008.80  5054.7 1007.45  5060.2 1009.17
  5077.3 1007.80  5082.8 1009.43  5099.9 1008.31  5105.4 1009.35  5122.4 1008.89
  5128.0 1009.80  5167.6 1009.99  5291.7 1014.36  5366.0 1015.00  5373.8 1015.28
  5380.3 1017.94  5394.6 1016.70  5401.1 1019.42  5423.2 1020.44  5655.6 1026.26
#Mann=3,-1,0
  4524.6    0.05       0  5030.0    0.03       0  5034.0    0.05       0
Bank Sta=5030,5034
Exp/Cntr=0.3,0.1

Type RM Length L Ch R = 1,18907,379,379,379
BEGIN DESCRIPTION:
Mapping XS fc09f8b2
END DESCRIPTION:
XS GIS Cut Line= 4
      2883455.51     10237064.19      2883043.16     10237059.85
      2882912.96     10237350.65      2882557.05     10237875.83
#Sta/Elev= 30
  4443.3 1015.51  4577.4 1012.24  4663.1 1010.17  4693.1 1010.54  4763.1 1008.94
  4773.1 1009.82  4833.1 1007.01  4880.9 1008.17  4925.0 1006.98  4956.0 1007.40
  4979.2 1006.63  4984.7 1003.85  4988.7 1003.11  4989.0 1002.61  4992.7 1003.11
  5007.9 1003.44  5013.3 1005.49  5031.0 1007.12  5067.4 1007.97  5111.6 1010.62
  5129.3 1010.33  5152.5 1011.70  5166.0 1013.58  5237.8 1016.61  5346.4 1018.43
  5369.5 1017.46  5396.5 1018.73  5441.3 1018.95  5627.1 1025.79  5808.7 1029.35
#Mann=4,-1,0
  4443.3    0.12       0  4577.4    0.05       0  4988.7    0.03       0
  4992.7    0.05       0
Bank Sta=4988.7,4992.7
Exp/Cntr=0.3,0.1

Type RM Length L Ch R = 1,18528,487,487,487
BEGIN DESCRIPTION:
FRENCH JOHN CREEK 38.0
END DESCRIPTION:
XS GIS Cut Line= 3
      2883455.66     10237003.10      2882898.00     10236828.00
      2882705.68     10237003.11
#Sta/Elev= 30
  4415.5 1015.68  4431.7 1014.31  4469.3 1013.23  4509.8 1012.87  4534.2 1011.72
  4669.0 1008.53  4696.2 1008.88  4708.9 1008.17  4719.4 1008.84  4766.3 1006.05
  4771.8 1007.56  4792.8 1007.78  4868.8 1006.46  4901.2 1004.84  4933.6 1005.35
  4939.5 1004.38  4950.0 1004.03  4966.0 1005.46  4991.9 1003.86  5003.0 1002.42
  5003.3 1001.92  5007.0 1002.42  5026.6 1003.47  5047.6 1003.61  5069.2 1005.54
  5076.0 1005.26  5084.9 1006.09  5137.8 1009.25  5210.4 1012.60  5260.1 1013.43
#Mann=5,-1,0
  4415.5    0.05       0  5003.0    0.05       0  5007.0    0.05       0
  5084.9    0.12       0  5137.8    0.05       0
Bank Sta=5003,5007
Exp/Cntr=0.3,0.1

Type RM Length L Ch R = 1,18041,485,485,485
BEGIN DESCRIPTION:
FRENCH JOHN CREEK 37.0
END DESCRIPTION:
XS GIS Cut Line= 3
      2883505.68     10236903.11      2883077.50     10236417.00
      2882455.67     10236703.12
#Sta/Elev= 30
  4352.2 1014.54  4387.8 1013.60  4394.4 1014.31  4422.9 1011.94  4458.8 1011.47
  4536.7 1007.77  4565.2 1007.94  4586.1 1006.15  4657.2 1003.52  4692.3 1003.52
  4741.7 1000.86  4763.4 1001.08  4770.1 1003.01  4855.5  998.57  4939.9  999.56
  4988.2  997.00  4988.4  996.50  4992.2  997.00  4996.9  997.99  5090.1  998.83
  5171.4 1003.97  5188.8 1004.11  5200.1 1006.04  5255.2 1007.77  5291.7 1007.37
  5325.8 1005.14  5383.6 1002.56  5471.3 1006.98  5607.4 1010.16  5684.5 1013.28
#Mann=5,-1,0
  4352.2    0.05       0  4988.2    0.03       0  4992.2    0.05       0
  5325.8    0.12       0  5471.3    0.05       0
Bank Sta=4988.2,4992.2
Exp/Cntr=0.3,0.1

Type RM Length L Ch R = 1,17556,715,715,715
BEGIN DESCRIPTION:
FRENCH JOHN CREEK 36.0
END DESCRIPTION:
XS GIS Cut Line= 3
      2883405.72     10235703.08      2883091.75     10236003.00
      2882555.65     10236303.13
#Sta/Elev= 30
  4565.8 1001.17  4672.0  998.06  4848.8  997.21  4856.0  995.49  4877.1  994.32
  4940.6  993.54  4976.1  991.32  4983.0  992.06  4996.5  989.37  5009.6  989.28
  5009.8  988.78  5013.6  989.28  5027.5  993.31  5033.3  993.98  5049.2  993.81
  5055.0  992.97  5064.3  993.59  5121.6  992.97  5201.8  997.34  5260.5  996.27
  5276.4  994.97  5327.8  997.11  5335.8  998.15  5341.5  997.19  5422.6  999.64
  5557.1 1005.44  5584.7 1005.90  5606.4 1007.13  5611.5 1008.61  5614.4 1008.61
#Mann=3,-1,0
  4565.8    0.05       0  5009.6    0.03       0  5013.6    0.05       0
Bank Sta=5009.6,5013.6
Exp/Cntr=0.3,0.1

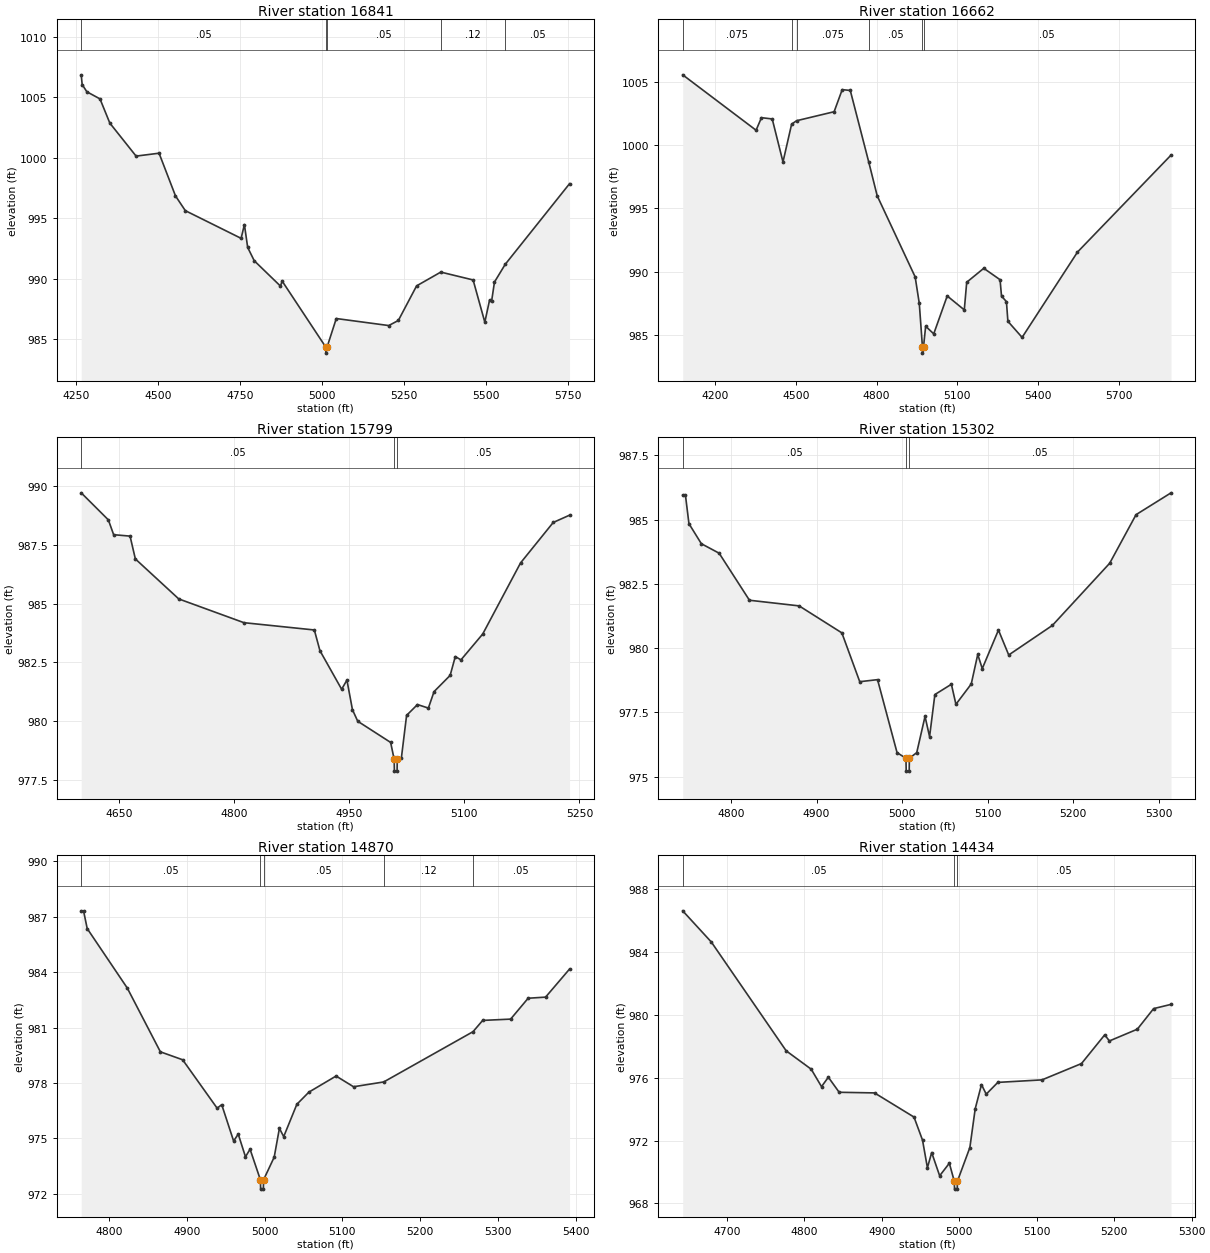
Type RM Length L Ch R = 1,16841,179,179,179
BEGIN DESCRIPTION:
Mapping XS d5fe1ee8
END DESCRIPTION:
XS GIS Cut Line= 4
      2883472.89     10235458.29      2882856.53     10235427.91
      2882509.31     10235414.89      2882080.54     10235718.06
#Sta/Elev= 30
  4264.9 1006.86  4267.8 1006.06  4282.1 1005.46  4322.2 1004.87  4352.2 1002.87
  4432.3 1000.14  4502.4 1000.38  4552.5  996.85  4582.5  995.63  4752.7  993.34
  4762.7  994.48  4772.7  992.59  4792.7  991.49  4872.8  989.39  4877.8  989.81
  5010.9  984.35  5011.2  983.85  5014.9  984.35  5043.0  986.71  5203.1  986.13
  5232.3  986.55  5288.0  989.41  5361.8  990.55  5460.4  989.90  5496.1  986.41
  5510.8  988.26  5517.0  988.18  5525.6  989.73  5558.3  991.19  5754.6  997.86
#Mann=5,-1,0
  4264.9    0.05       0  5010.9    0.03       0  5014.9    0.05       0
  5361.8    0.12       0  5558.3    0.05       0
Bank Sta=5010.9,5014.9
Exp/Cntr=0.3,0.1

Type RM Length L Ch R = 1,16662,863,863,863
BEGIN DESCRIPTION:
Mapping XS ab46bade
END DESCRIPTION:
XS GIS Cut Line= 4
      2883568.32     10235267.32      2882704.62     10235267.32
      2882522.33     10235276.00      2881814.90     10235575.46
#Sta/Elev= 30
  4079.5 1005.54  4352.1 1001.17  4372.1 1002.16  4412.1 1002.06  4452.1  998.67
  4484.2 1001.65  4502.6 1001.92  4642.1 1002.63  4672.1 1004.37  4702.1 1004.31
  4771.0  998.64  4802.1  996.00  4943.2  989.60  4958.5  987.51  4970.2  984.09
  4970.4  983.59  4974.2  984.09  4982.2  985.71  5012.2  985.11  5062.3  988.10
  5125.7  987.00  5134.7  989.18  5198.1  990.28  5258.6  989.38  5264.0  988.09
  5282.3  987.65  5287.7  986.10  5340.5  984.83  5546.3  991.56  5893.9  999.21
#Mann=6,-1,0
  4079.5   0.075       0  4484.2    0.05       0  4502.6   0.075       0
  4771.0    0.05       0  4970.2    0.03       0  4974.2    0.05       0
Bank Sta=4970.2,4974.2
Exp/Cntr=0.3,0.1

Type RM Length L Ch R = 1,15799,497,497,497
BEGIN DESCRIPTION:
FRENCH JOHN CREEK 32.0
END DESCRIPTION:
XS GIS Cut Line= 3
      2882305.68     10234703.11      2882030.50     10234993.00
      2881855.65     10235153.14
#Sta/Elev= 30
  4600.3  989.71  4635.7  988.56  4642.6  987.93  4664.0  987.87  4670.9  986.90
  4727.5  985.20  4812.5  984.19  4904.3  983.88  4911.6  983.00  4939.9  981.36
  4946.8  981.75  4954.0  980.49  4960.9  980.00  5003.8  979.10  5008.4  978.38
  5008.7  977.88  5012.2  977.88  5012.4  978.38  5017.8  978.44  5024.6  980.25
  5038.8  980.71  5053.0  980.56  5060.4  981.26  5081.4  981.95  5088.1  982.75
  5095.5  982.61  5123.9  983.71  5173.2  986.73  5215.8  988.45  5237.1  988.76
#Mann=3,-1,0
  4600.3    0.05       0  5008.4    0.03       0  5012.4    0.05       0
Bank Sta=5008.4,5012.4
Exp/Cntr=0.3,0.1

Type RM Length L Ch R = 1,15302,432,432,432
BEGIN DESCRIPTION:
FRENCH JOHN CREEK 31.0
END DESCRIPTION:
XS GIS Cut Line= 3
      2881755.70     10234553.10      2881600.25     10234757.00
      2881705.68     10235053.09
#Sta/Elev= 30
  4743.6  985.95  4746.8  985.95  4750.9  984.84  4765.4  984.06  4786.2  983.69
  4821.6  981.86  4879.7  981.64  4929.6  980.59  4950.5  978.69  4971.3  978.77
  4994.1  975.93  5004.5  975.71  5004.8  975.21  5008.3  975.21  5008.5  975.71
  5017.1  975.93  5026.8  977.34  5032.1  976.55  5038.3  978.19  5057.6  978.59
  5062.9  977.81  5080.8  978.60  5088.4  979.75  5093.7  979.20  5112.6  980.70
  5124.6  979.73  5175.6  980.88  5242.6  983.30  5273.4  985.19  5314.3  986.04
#Mann=3,-1,0
  4743.6    0.05       0  5004.5    0.05       0  5008.5    0.05       0
Bank Sta=5004.5,5008.5
Exp/Cntr=0.3,0.1

Type RM Length L Ch R = 1,14870,436,436,436
BEGIN DESCRIPTION:
FRENCH JOHN CREEK 30.0
END DESCRIPTION:
XS GIS Cut Line= 3
      2881055.67     10234453.09      2881181.75     10234652.00
      2881355.67     10235003.08
#Sta/Elev= 30
  4764.5  987.32  4767.5  987.32  4772.2  986.36  4823.7  983.14  4866.2  979.69
  4894.8  979.26  4939.1  976.64  4945.0  976.83  4960.3  974.86  4966.2  975.24
  4975.5  974.01  4981.4  974.42  4994.7  972.76  4995.0  972.26  4998.5  972.26
  4998.7  972.76  5012.4  973.99  5019.1  975.55  5024.6  975.10  5041.5  976.85
  5057.0  977.51  5091.9  978.38  5114.3  977.80  5153.1  978.06  5267.8  980.78
  5280.2  981.39  5316.1  981.46  5338.6  982.59  5361.0  982.65  5391.8  984.17
#Mann=5,-1,0
  4764.5    0.05       0  4994.7    0.05       0  4998.7    0.05       0
  5153.1    0.12       0  5267.8    0.05       0
Bank Sta=4994.7,4998.7
Exp/Cntr=0.3,0.1

Type RM Length L Ch R = 1,14434,471,471,471
BEGIN DESCRIPTION:
FRENCH JOHN CREEK 29.0
END DESCRIPTION:
XS GIS Cut Line= 3
      2880955.70     10234453.07      2880803.50     10234776.00
      2880955.69     10235003.12
#Sta/Elev= 30
  4643.0  986.64  4680.0  984.65  4776.6  977.72  4808.9  976.55  4822.2  975.44
  4831.0  976.04  4845.0  975.08  4890.6  975.04  4941.6  973.50  4952.6  972.03
  4958.9  970.27  4964.4  971.24  4974.7  969.76  4987.2  970.56  4993.6  969.41
  4993.9  968.91  4997.4  968.91  4997.6  969.41  5013.7  971.56  5020.6  974.03
  5028.7  975.57  5034.8  974.96  5049.8  975.71  5106.8  975.87  5157.8  976.91
  5187.8  978.74  5193.8  978.35  5229.9  979.10  5250.9  980.41  5273.4  980.68
#Mann=3,-1,0
  4643.0    0.05       0  4993.6    0.05       0  4997.6    0.05       0
Bank Sta=4993.6,4997.6
Exp/Cntr=0.3,0.1

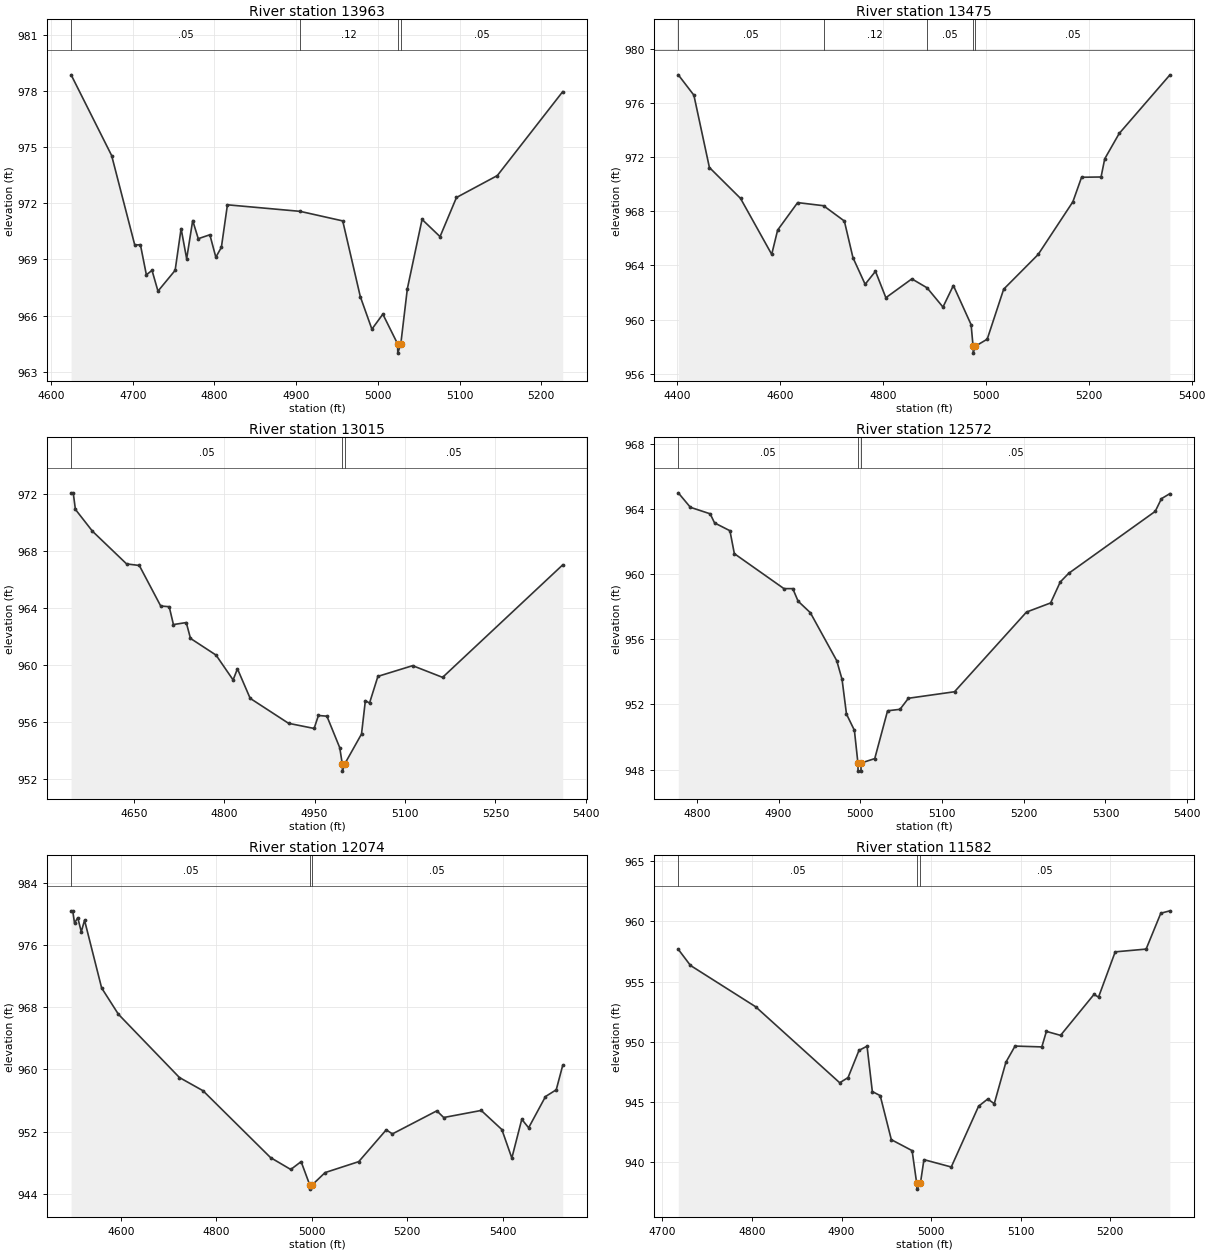
Type RM Length L Ch R = 1,13963,488,488,488
BEGIN DESCRIPTION:
FRENCH JOHN CREEK 28.0
END DESCRIPTION:
XS GIS Cut Line= 3
      2880605.71     10234453.09      2880349.00     10234727.00
      2880355.68     10234953.10
#Sta/Elev= 30
  4624.6  978.86  4674.2  974.55  4702.5  969.77  4709.4  969.79  4716.7  968.18
  4723.6  968.42  4730.9  967.31  4751.9  968.42  4759.2  970.65  4766.0  969.04
  4773.4  971.08  4780.2  970.11  4794.4  970.32  4801.7  969.12  4808.5  969.65
  4815.9  971.92  4904.9  971.57  4957.0  971.06  4978.5  967.02  4992.7  965.28
  5006.1  966.08  5024.1  964.50  5024.4  964.00  5028.1  964.50  5036.1  967.44
  5054.1  971.14  5076.1  970.22  5096.2  972.31  5146.2  973.48  5226.2  977.96
#Mann=4,-1,0
  4624.6    0.05       0  4904.9    0.12       0  5024.1    0.07       0
  5028.1    0.05       0
Bank Sta=5024.1,5028.1
Exp/Cntr=0.3,0.1

Type RM Length L Ch R = 1,13475,460,460,460
BEGIN DESCRIPTION:
FRENCH JOHN CREEK 27.0
END DESCRIPTION:
XS GIS Cut Line= 3
      2880555.67     10234353.11      2879963.00     10234432.00
      2879805.67     10234753.13
#Sta/Elev= 30
  4402.1  978.06  4432.4  976.56  4462.6  971.22  4523.1  968.94  4583.7  964.81
  4595.2  966.60  4634.1  968.63  4684.4  968.40  4724.9  967.27  4741.6  964.57
  4765.3  962.60  4785.4  963.56  4805.6  961.61  4856.1  963.00  4885.7  962.34
  4916.6  960.92  4936.8  962.51  4971.3  959.62  4975.1  958.02  4975.4  957.52
  4979.1  958.02  5002.6  958.55  5034.6  962.24  5101.6  964.80  5169.1  968.69
  5186.0  970.50  5223.9  970.52  5231.0  971.86  5259.1  973.73  5357.6  978.05
#Mann=5,-1,0
  4402.1    0.05       0  4684.4    0.12       0  4885.7    0.05       0
  4975.1    0.05       0  4979.1    0.05       0
Bank Sta=4975.1,4979.1
Exp/Cntr=0.3,0.1

Type RM Length L Ch R = 1,13015,443,443,443
BEGIN DESCRIPTION:
FRENCH JOHN CREEK 26.0
END DESCRIPTION:
XS GIS Cut Line= 3
      2880005.71     10233803.08      2879681.75     10234121.00
      2879455.69     10234403.10
#Sta/Elev= 30
  4546.1  972.08  4549.6  972.08  4553.2  970.92  4581.5  969.39  4638.1  967.10
  4659.2  966.99  4694.7  964.15  4708.8  964.10  4715.8  962.85  4737.1  962.99
  4744.1  961.88  4786.5  960.71  4814.8  958.97  4822.0  959.75  4843.1  957.68
  4906.8  955.93  4949.2  955.57  4956.3  956.48  4970.4  956.43  4991.7  954.22
  4995.9  953.08  4996.2  952.58  4999.9  953.08  5027.8  955.18  5034.2  957.52
  5041.1  957.35  5055.0  959.22  5112.6  959.97  5162.3  959.15  5361.5  967.03
#Mann=3,-1,0
  4546.1    0.05       0  4995.9    0.05       0  4999.9    0.05       0
Bank Sta=4995.9,4999.9
Exp/Cntr=0.3,0.1

Type RM Length L Ch R = 1,12572,498,498,498
BEGIN DESCRIPTION:
FRENCH JOHN CREEK 25.0
END DESCRIPTION:
XS GIS Cut Line= 3
      2879605.70     10233703.11      2879399.00     10233786.00
      2879305.68     10234153.13
#Sta/Elev= 30
  4777.3  965.01  4792.1  964.12  4816.3  963.72  4821.7  963.16  4840.5  962.68
  4845.9  961.27  4906.6  959.12  4917.4  959.12  4923.9  958.35  4938.9  957.64
  4971.2  954.69  4977.7  953.54  4983.1  951.41  4992.8  950.41  4997.1  948.40
  4997.3  947.90  5000.8  947.90  5001.1  948.40  5017.7  948.67  5033.4  951.61
  5048.6  951.70  5058.9  952.38  5115.3  952.78  5203.4  957.68  5232.9  958.24
  5244.7  959.53  5255.0  960.06  5360.9  963.87  5368.5  964.65  5378.8  964.96
#Mann=3,-1,0
  4777.3    0.05       0  4997.1    0.05       0  5001.1    0.05       0
Bank Sta=4997.1,5001.1
Exp/Cntr=0.3,0.1

Type RM Length L Ch R = 1,12074,492,492,492
BEGIN DESCRIPTION:
FRENCH JOHN CREEK 24.0
END DESCRIPTION:
XS GIS Cut Line= 3
      2879455.71     10233103.09      2879081.50     10233441.00
      2878755.71     10233853.07
#Sta/Elev= 30
  4495.8  980.42  4499.2  980.42  4502.9  978.85  4509.7  979.53  4517.1  977.72
  4523.9  979.21  4559.7  970.49  4594.9  967.10  4722.6  958.96  4772.0  957.26
  4913.5  948.65  4955.8  947.12  4977.5  948.13  4995.8  945.09  4996.0  944.59
  4999.9  945.09  5027.7  946.72  5098.2  948.13  5155.7  952.22  5168.7  951.70
  5261.7  954.67  5276.1  953.81  5354.7  954.72  5397.9  952.26  5418.8  948.59
  5439.6  953.58  5454.0  952.49  5489.3  956.51  5511.8  957.38  5525.3  960.51
#Mann=3,-1,0
  4495.8    0.05       0  4995.8    0.03       0  4999.9    0.05       0
Bank Sta=4995.8,4999.9
Exp/Cntr=0.3,0.1

Type RM Length L Ch R = 1,11582,491,491,491
BEGIN DESCRIPTION:
FRENCH JOHN CREEK 23.0
END DESCRIPTION:
XS GIS Cut Line= 3
      2878855.70     10233153.10      2878617.75     10233305.00
      2878355.73     10233353.10
#Sta/Elev= 30
  4717.7  957.68  4731.3  956.34  4804.0  952.91  4897.9  946.59  4907.2  947.02
  4919.4  949.28  4928.4  949.63  4934.3  945.86  4943.1  945.52  4955.5  941.86
  4978.7  940.95  4983.8  938.25  4984.1  937.75  4988.0  938.25  4991.9  940.20
  5022.4  939.59  5052.9  944.64  5063.1  945.24  5070.4  944.85  5083.4  948.30
  5093.6  949.64  5123.5  949.57  5128.6  950.86  5144.4  950.53  5181.7  953.93
  5186.8  953.71  5205.4  957.47  5239.9  957.70  5256.3  960.68  5266.4  960.88
#Mann=3,-1,0
  4717.7    0.05       0  4983.8    0.05       0  4988.0    0.05       0
Bank Sta=4983.8,4988
Exp/Cntr=0.3,0.1

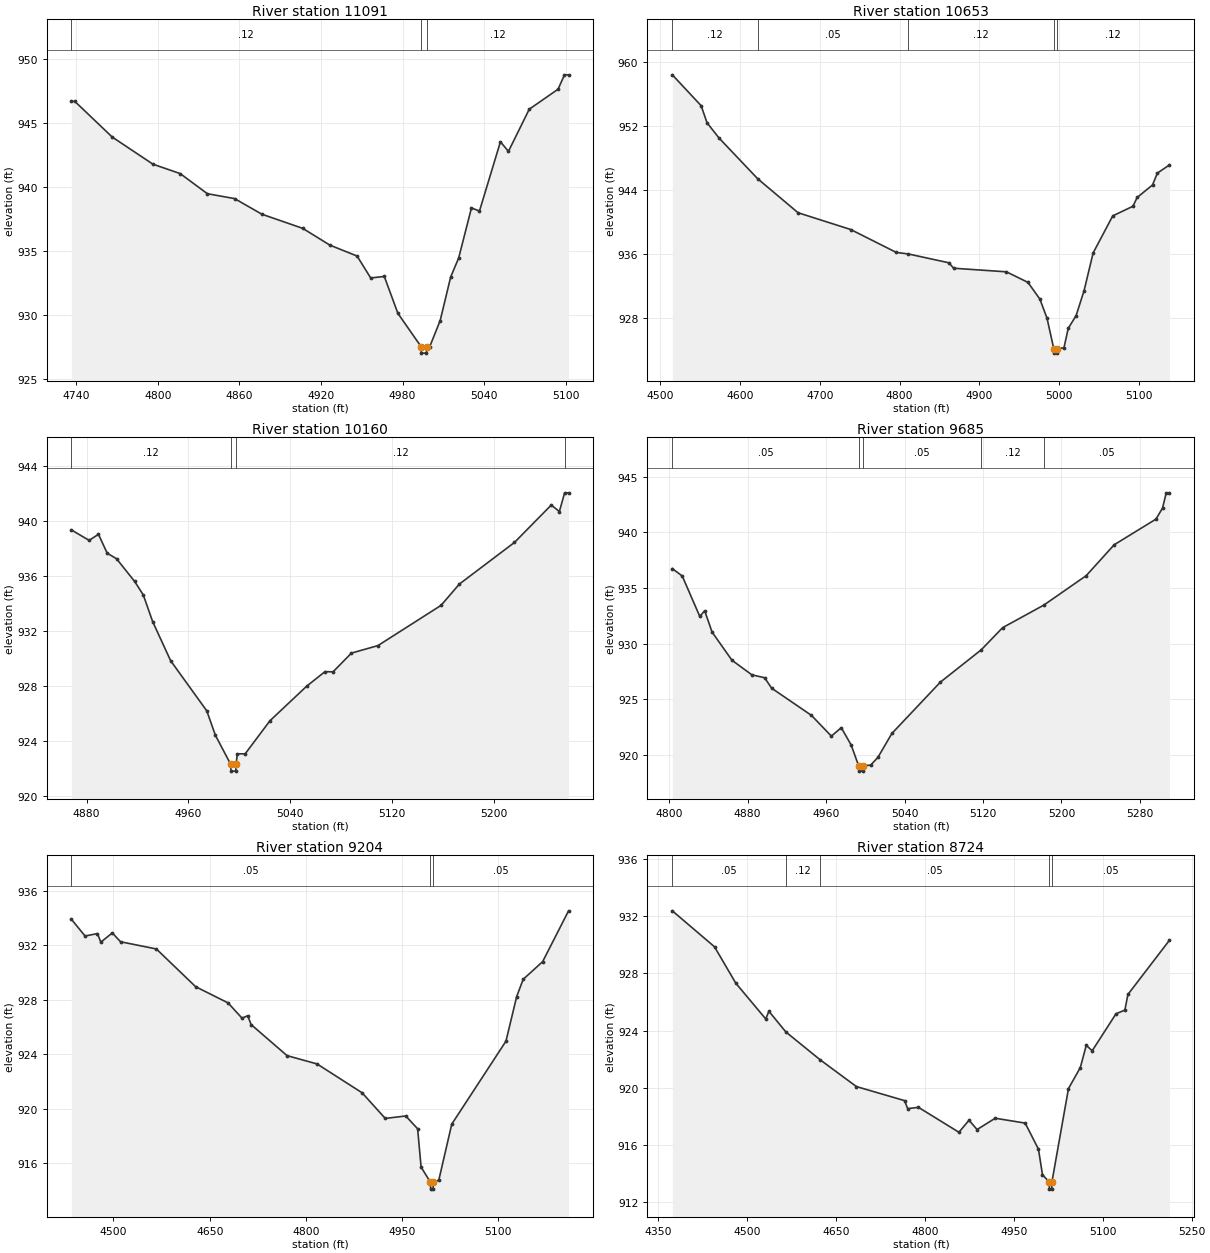
Type RM Length L Ch R = 1,11091,438,438,438
BEGIN DESCRIPTION:
FRENCH JOHN CREEK 22.0
END DESCRIPTION:
XS GIS Cut Line= 3
      2878555.72     10232953.11      2878292.25     10232949.00
      2878205.67     10233003.12
#Sta/Elev= 30
  4736.5  946.66  4739.0  946.66  4766.5  943.88  4796.5  941.76  4816.5  941.03
  4836.5  939.46  4856.5  939.08  4876.6  937.86  4906.6  936.76  4926.6  935.45
  4946.6  934.60  4956.6  932.89  4966.6  933.01  4976.6  930.13  4993.7  927.53
  4993.9  927.03  4997.6  927.03  4997.9  927.53  5000.0  927.53  5007.7  929.57
  5015.4  932.96  5021.3  934.45  5030.7  938.35  5036.6  938.11  5052.0  943.51
  5057.9  942.76  5073.2  946.05  5094.4  947.61  5099.1  948.73  5102.1  948.73
#Mann=3,-1,0
  4736.5    0.12       0  4993.7    0.07       0  4997.9    0.12       0
Bank Sta=4993.7,4997.9
Exp/Cntr=0.3,0.1

Type RM Length L Ch R = 1,10653,493,493,493
BEGIN DESCRIPTION:
FRENCH JOHN CREEK 21.0
END DESCRIPTION:
XS GIS Cut Line= 3
      2878855.70     10232853.12      2878453.00     10232583.00
      2878405.70     10232453.15
#Sta/Elev= 30
  4515.1  958.45  4551.2  954.59  4558.6  952.45  4573.6  950.55  4622.2  945.44
  4672.7  941.20  4738.7  939.10  4795.7  936.24  4811.0  936.04  4861.7  934.94
  4867.7  934.26  4933.8  933.81  4960.8  932.49  4975.8  930.39  4984.7  928.01
  4993.3  924.14  4993.6  923.64  4997.3  923.64  4997.5  924.14  5006.0  924.33
  5011.3  926.74  5021.2  928.34  5031.2  931.47  5042.5  936.17  5067.1  940.81
  5092.4  942.01  5097.7  943.11  5117.0  944.68  5123.0  946.16  5138.2  947.18
#Mann=5,-1,0
  4515.1    0.12       0  4622.2    0.05       0  4811.0    0.12       0
  4993.3    0.07       0  4997.5    0.12       0
Bank Sta=4993.3,4997.5
Exp/Cntr=0.3,0.1

Type RM Length L Ch R = 1,10160,475,475,475
BEGIN DESCRIPTION:
FRENCH JOHN CREEK 20.0
END DESCRIPTION:
XS GIS Cut Line= 3
      2878955.72     10232503.14      2878858.50     10232414.00
      2878655.67     10232253.10
#Sta/Elev= 30
  4868.1  939.37  4882.0  938.61  4889.4  939.05  4896.2  937.68  4903.6  937.27
  4917.8  935.62  4924.6  934.64  4932.0  932.69  4946.1  929.85  4974.5  926.20
  4981.3  924.42  4993.3  922.31  4993.6  921.81  4997.3  921.81  4997.6  922.31
  4998.5  923.07  5004.7  923.07  5024.2  925.48  5053.0  927.99  5067.4  929.05
  5073.8  929.04  5088.2  930.40  5109.1  930.95  5158.7  933.88  5173.1  935.43
  5216.4  938.46  5245.3  941.18  5251.7  940.71  5255.8  942.07  5258.9  942.07
#Mann=4,-1,0
  4868.1    0.12       0  4993.3    0.07       0  4997.6    0.12       0
  5255.8    0.05       0
Bank Sta=4993.3,4997.6
Exp/Cntr=0.3,0.1

Type RM Length L Ch R = 1,9685,481,481,481
BEGIN DESCRIPTION:
FRENCH JOHN CREEK 19.0
END DESCRIPTION:
XS GIS Cut Line= 3
      2879055.66     10232003.11      2878861.50     10231971.00
      2878655.70     10232203.10
#Sta/Elev= 30
  4803.2  936.74  4813.3  936.08  4831.2  932.45  4836.2  932.96  4843.7  931.05
  4864.0  928.52  4884.3  927.21  4897.3  926.95  4904.5  926.01  4945.1  923.57
  4965.4  921.71  4975.5  922.47  4985.6  920.91  4993.1  919.07  4993.4  918.57
  4997.2  918.57  4997.5  919.07  5005.4  919.10  5012.9  919.81  5027.1  921.95
  5076.5  926.55  5118.3  929.46  5140.0  931.44  5182.1  933.47  5225.3  936.11
  5253.8  938.88  5296.4  941.18  5303.1  942.17  5306.9  943.54  5310.2  943.54
#Mann=5,-1,0
  4803.2    0.05       0  4993.1    0.05       0  4997.5    0.05       0
  5118.3    0.12       0  5182.1    0.05       0
Bank Sta=4993.1,4997.5
Exp/Cntr=0.3,0.1

Type RM Length L Ch R = 1,9204,480,480,480
BEGIN DESCRIPTION:
FRENCH JOHN CREEK 18.0
END DESCRIPTION:
XS GIS Cut Line= 3
      2878955.69     10231603.11      2878424.00     10231796.00
      2878455.68     10232003.09
#Sta/Elev= 30
  4434.4  933.90  4455.7  932.67  4475.0  932.85  4480.3  932.22  4498.2  932.90
  4511.0  932.25  4566.9  931.72  4628.1  928.95  4678.7  927.76  4700.4  926.64
  4709.3  926.82  4714.6  926.17  4770.6  923.89  4817.4  923.28  4887.7  921.16
  4923.7  919.28  4955.7  919.46  4974.2  918.52  4979.6  915.71  4994.2  914.59
  4994.5  914.09  4998.3  914.09  4998.6  914.59  5007.2  914.75  5027.4  918.86
  5111.9  924.95  5128.6  928.22  5138.7  929.49  5169.1  930.79  5209.5  934.52
#Mann=3,-1,0
  4434.4    0.05       0  4994.2    0.05       0  4998.6    0.05       0
Bank Sta=4994.2,4998.6
Exp/Cntr=0.3,0.1

Type RM Length L Ch R = 1,8724,495,495,495
BEGIN DESCRIPTION:
FRENCH JOHN CREEK 17.0
END DESCRIPTION:
XS GIS Cut Line= 3
      2878855.68     10231603.11      2878267.75     10231389.00
      2878055.72     10231403.11
#Sta/Elev= 30
  4374.3  932.36  4445.4  929.85  4481.3  927.31  4531.8  924.81  4537.1  925.35
  4565.8  923.90  4623.5  921.96  4684.7  920.09  4765.8  919.11  4771.1  918.55
  4789.3  918.64  4857.5  916.90  4874.5  917.74  4888.1  917.09  4918.7  917.88
  4969.2  917.54  4991.6  915.72  4998.4  913.93  5009.8  913.43  5010.1  912.93
  5014.0  912.93  5014.3  913.43  5042.2  919.95  5062.2  921.42  5072.2  922.97
  5082.2  922.59  5122.3  925.17  5137.3  925.43  5142.4  926.52  5212.5  930.31
#Mann=5,-1,0
  4374.3    0.05       0  4565.8    0.12       0  4623.5    0.05       0
  5009.8    0.05       0  5014.3    0.05       0
Bank Sta=5009.8,5014.3
Exp/Cntr=0.3,0.1