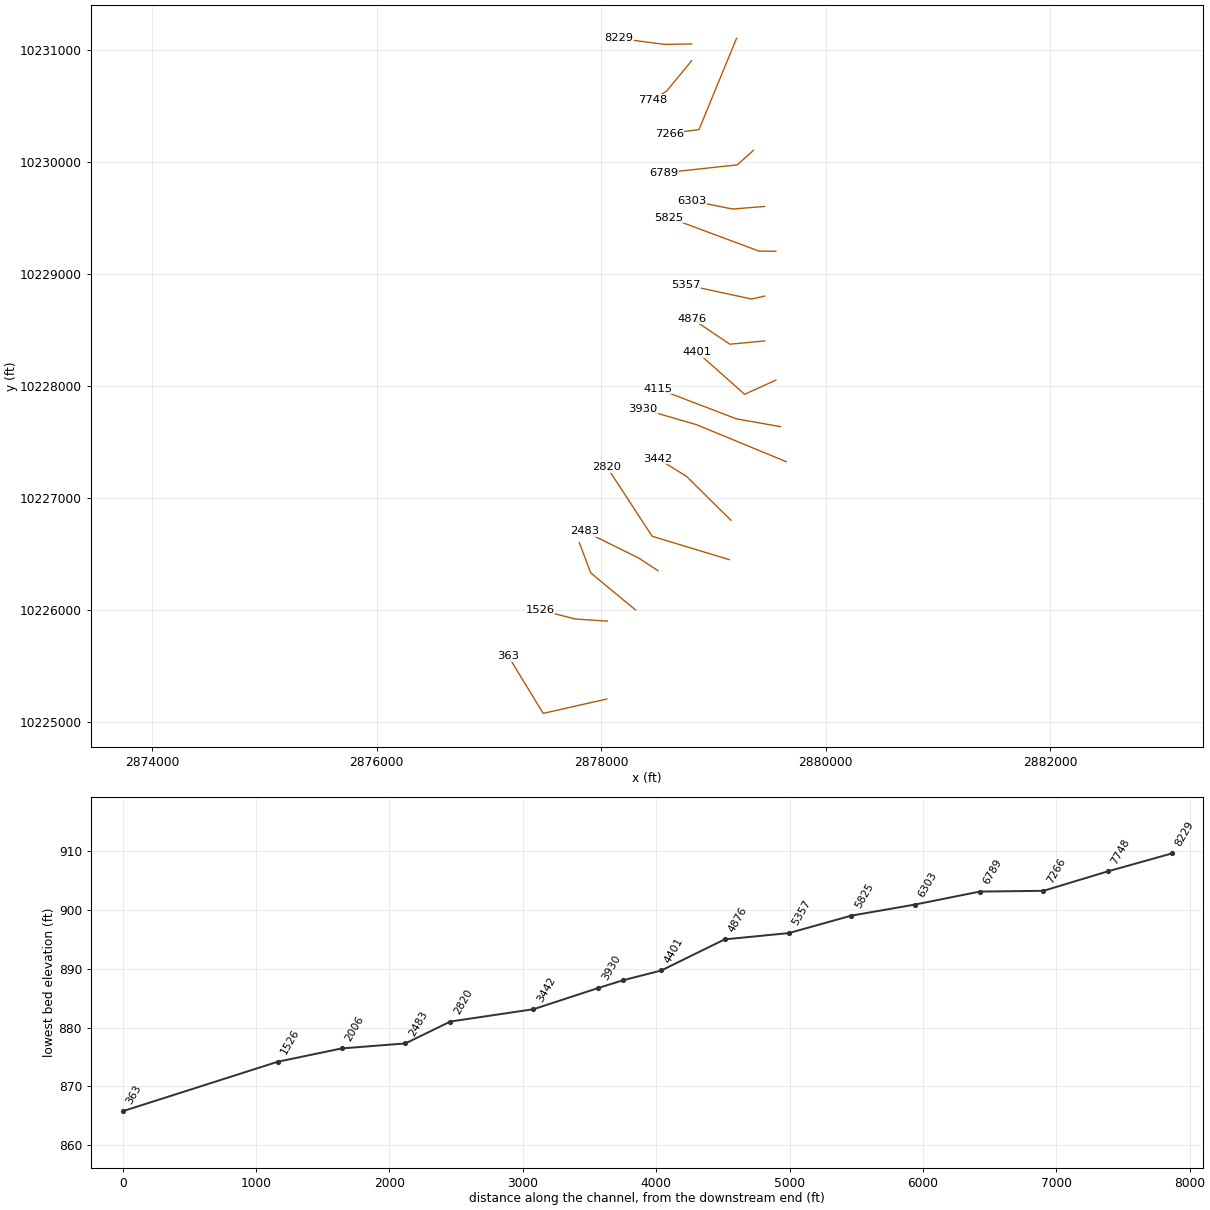
HEC-RAS study FRENCH JOHN CREEK.prj: FRENCH JOHN CREEK Base Level Engineering

--- FRENCH JOHN CREEK.g01 (geometry) --- (continued)

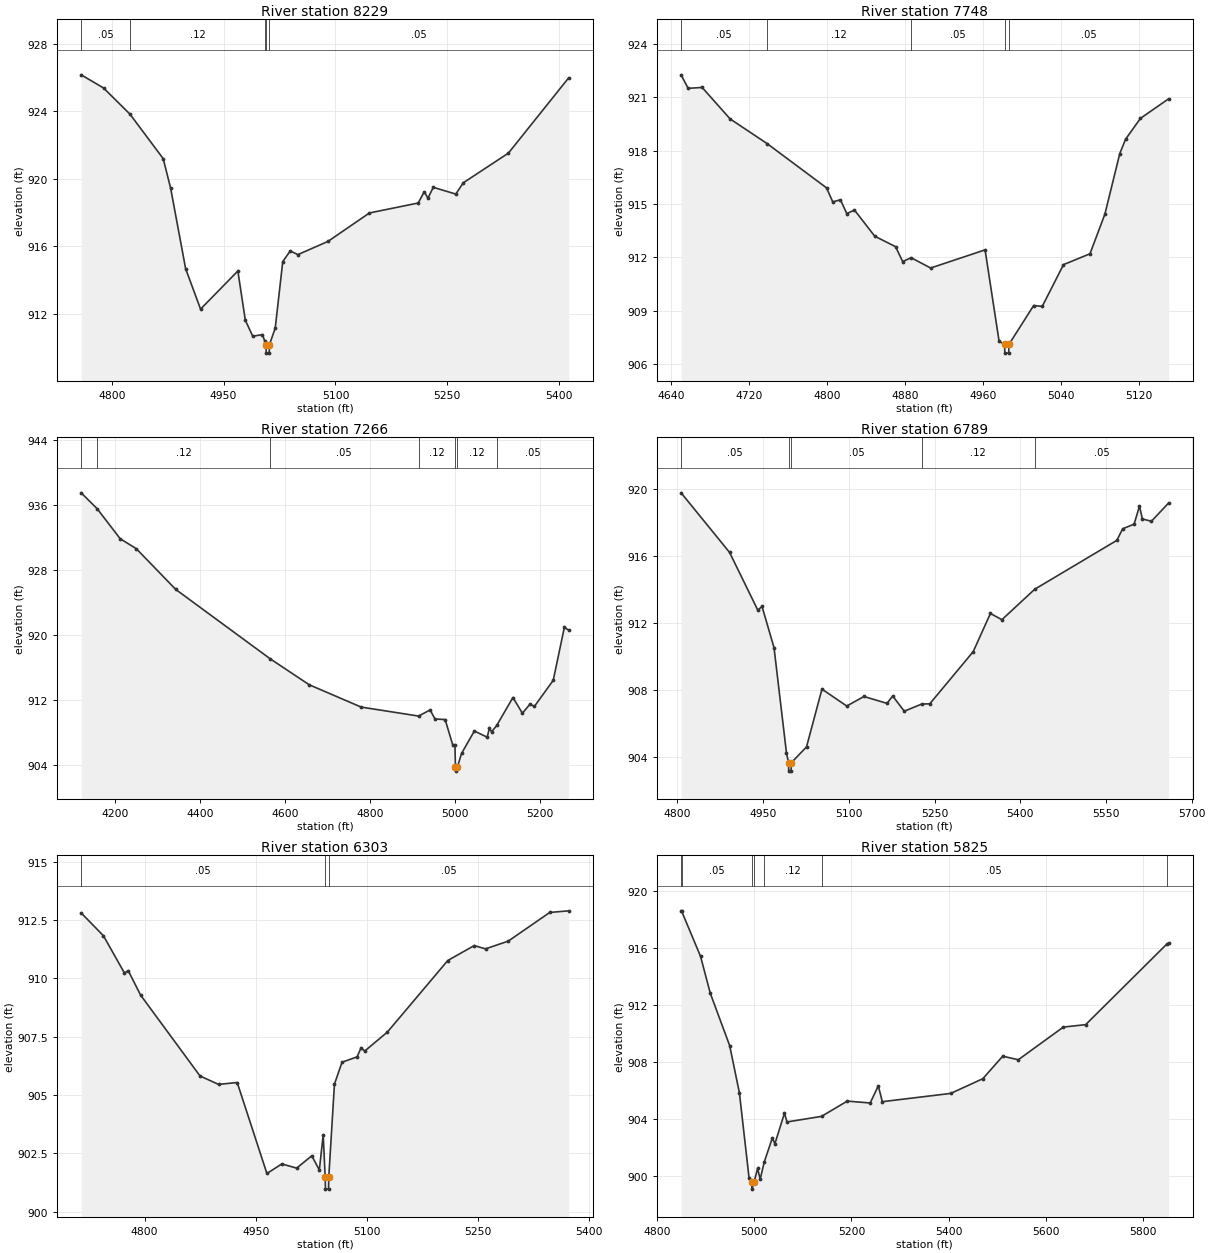
Type RM Length L Ch R = 1,8229,481,481,481
BEGIN DESCRIPTION:
FRENCH JOHN CREEK 16.0
END DESCRIPTION:
XS GIS Cut Line= 3
      2878805.71     10231053.11      2878564.75     10231049.00
      2878155.71     10231103.11
#Sta/Elev= 30
  4759.0  926.17  4789.0  925.39  4824.4  923.84  4869.0  921.20  4879.0  919.44
  4899.1  914.67  4919.1  912.28  4969.1  914.54  4979.1  911.62  4989.1  910.67
  5002.1  910.77  5005.3  910.36  5006.8  910.17  5007.2  909.67  5011.1  909.67
  5011.4  910.17  5019.2  911.15  5029.3  915.10  5039.4  915.73  5049.5  915.51
  5089.8  916.29  5145.5  917.98  5210.9  918.57  5219.0  919.23  5224.0  918.86
  5231.1  919.50  5261.3  919.10  5271.4  919.77  5331.9  921.53  5412.6  925.99
#Mann=5,-1,0
  4759.0    0.05       0  4824.4    0.12       0  5005.3    0.05       0
  5006.8    0.07       0  5011.4    0.05       0
Bank Sta=5006.8,5011.4
Exp/Cntr=0.3,0.1

Type RM Length L Ch R = 1,7748,482,482,482
BEGIN DESCRIPTION:
FRENCH JOHN CREEK 15.0
END DESCRIPTION:
XS GIS Cut Line= 3
      2878805.72     10230903.15      2878583.50     10230633.00
      2878455.71     10230553.13
#Sta/Elev= 30
  4650.2  922.27  4657.4  921.51  4671.8  921.56  4700.5  919.79  4738.5  918.40
  4799.5  915.91  4805.9  915.12  4813.8  915.24  4820.3  914.46  4828.2  914.66
  4849.0  913.19  4870.4  912.60  4877.7  911.76  4886.3  911.98  4906.4  911.40
  4962.3  912.42  4976.7  907.27  4982.3  907.11  4982.6  906.61  4986.5  906.61
  4986.9  907.11  5012.2  909.29  5021.0  909.24  5042.8  911.59  5070.0  912.20
  5085.3  914.43  5100.6  917.84  5106.5  918.64  5121.8  919.82  5150.7  920.92
#Mann=5,-1,0
  4650.2    0.05       0  4738.5    0.12       0  4886.3    0.05       0
  4982.3    0.05       0  4986.9    0.05       0
Bank Sta=4982.3,4986.9
Exp/Cntr=0.3,0.1

Type RM Length L Ch R = 1,7266,477,477,477
BEGIN DESCRIPTION:
FRENCH JOHN CREEK 14.0
END DESCRIPTION:
XS GIS Cut Line= 3
      2879205.68     10231103.09      2878871.00     10230289.00
      2878605.72     10230253.12
#Sta/Elev= 30
  4119.8  937.51  4157.4  935.56  4211.8  931.86  4249.5  930.65  4342.4  925.64
  4564.6  917.12  4657.0  913.91  4779.3  911.17  4914.3  910.07  4941.5  910.82
  4953.0  909.71  4976.9  909.64  4995.1  906.47  5000.0  906.47  5001.2  903.80
  5001.5  903.30  5005.8  903.80  5015.5  905.47  5045.7  908.23  5076.0  907.47
  5081.1  908.60  5086.2  908.13  5098.3  908.91  5136.5  912.35  5158.8  910.42
  5176.9  911.54  5187.0  911.25  5231.4  914.46  5257.6  920.96  5267.7  920.64
#Mann=7,-1,0
  4119.8    0.05       0  4157.4    0.12       0  4564.6    0.05       0
  4914.3    0.12       0  5001.2    0.07       0  5005.8    0.12       0
  5098.3    0.05       0
Bank Sta=5001.2,5005.8
Exp/Cntr=0.3,0.1

Type RM Length L Ch R = 1,6789,486,486,486
BEGIN DESCRIPTION:
FRENCH JOHN CREEK 13.0
END DESCRIPTION:
XS GIS Cut Line= 3
      2879355.65     10230103.08      2879211.50     10229974.00
      2878555.72     10229903.12
#Sta/Elev= 30
  4806.5  919.80  4891.3  916.24  4940.7  912.79  4948.1  913.01  4969.1  910.55
  4990.8  904.28  4994.5  903.67  4994.9  903.17  4999.0  903.17  4999.3  903.67
  5026.0  904.62  5053.0  908.07  5096.4  907.06  5126.5  907.63  5166.8  907.22
  5176.8  907.66  5197.0  906.75  5227.7  907.18  5241.6  907.19  5317.7  910.31
  5347.8  912.59  5367.9  912.22  5425.4  914.04  5569.1  916.96  5579.2  917.65
  5599.3  917.93  5608.7  919.01  5613.7  918.24  5629.5  918.10  5659.6  919.19
#Mann=5,-1,0
  4806.5    0.05       0  4994.5    0.05       0  4999.3    0.05       0
  5227.7    0.12       0  5425.4    0.05       0
Bank Sta=4994.5,4999.3
Exp/Cntr=0.3,0.1

Type RM Length L Ch R = 1,6303,478,478,478
BEGIN DESCRIPTION:
FRENCH JOHN CREEK 12.0
END DESCRIPTION:
XS GIS Cut Line= 3
      2879455.66     10229603.11      2879171.00     10229580.00
      2878805.64     10229653.12
#Sta/Elev= 30
  4714.4  912.80  4744.5  911.82  4772.9  910.22  4777.9  910.33  4794.6  909.28
  4874.9  905.81  4899.9  905.45  4925.1  905.53  4965.2  901.63  4985.3  902.04
  5005.4  901.86  5025.8  902.39  5036.0  901.78  5041.2  903.29  5043.9  901.46
  5044.3  900.96  5048.4  900.96  5048.7  901.46  5056.4  905.46  5066.6  906.40
  5087.0  906.63  5092.2  907.01  5097.3  906.88  5127.8  907.69  5209.4  910.76
  5245.1  911.40  5260.4  911.26  5291.0  911.59  5347.1  912.82  5372.6  912.89
#Mann=3,-1,0
  4714.4    0.05       0  5043.9    0.05       0  5048.7    0.05       0
Bank Sta=5043.9,5048.7
Exp/Cntr=0.3,0.1

Type RM Length L Ch R = 1,5825,468,468,468
BEGIN DESCRIPTION:
FRENCH JOHN CREEK 11.0
END DESCRIPTION:
XS GIS Cut Line= 3
      2879555.69     10229203.11      2879405.00     10229205.00
      2878605.68     10229503.11
#Sta/Elev= 30
  4849.3  918.58  4850.1  918.58  4889.3  915.39  4909.3  912.81  4949.3  909.13
  4969.3  905.83  4989.3  899.83  4994.7  899.57  4995.1  899.07  4999.7  899.57
  5006.8  900.53  5012.1  899.76  5020.5  900.97  5037.1  902.65  5042.4  902.25
  5062.1  904.39  5067.4  903.78  5138.4  904.17  5191.4  905.24  5238.6  905.11
  5255.4  906.31  5263.6  905.20  5404.5  905.78  5470.5  906.81  5511.6  908.39
  5543.6  908.14  5636.4  910.43  5682.3  910.60  5849.2  916.24  5853.1  916.31
#Mann=7,-1,0
  4849.3    0.12       0  4850.1    0.05       0  4994.7    0.05       0
  4999.7    0.05       0  5020.5    0.12       0  5138.4    0.05       0
  5849.2    0.12       0
Bank Sta=4994.7,4999.7
Exp/Cntr=0.3,0.1

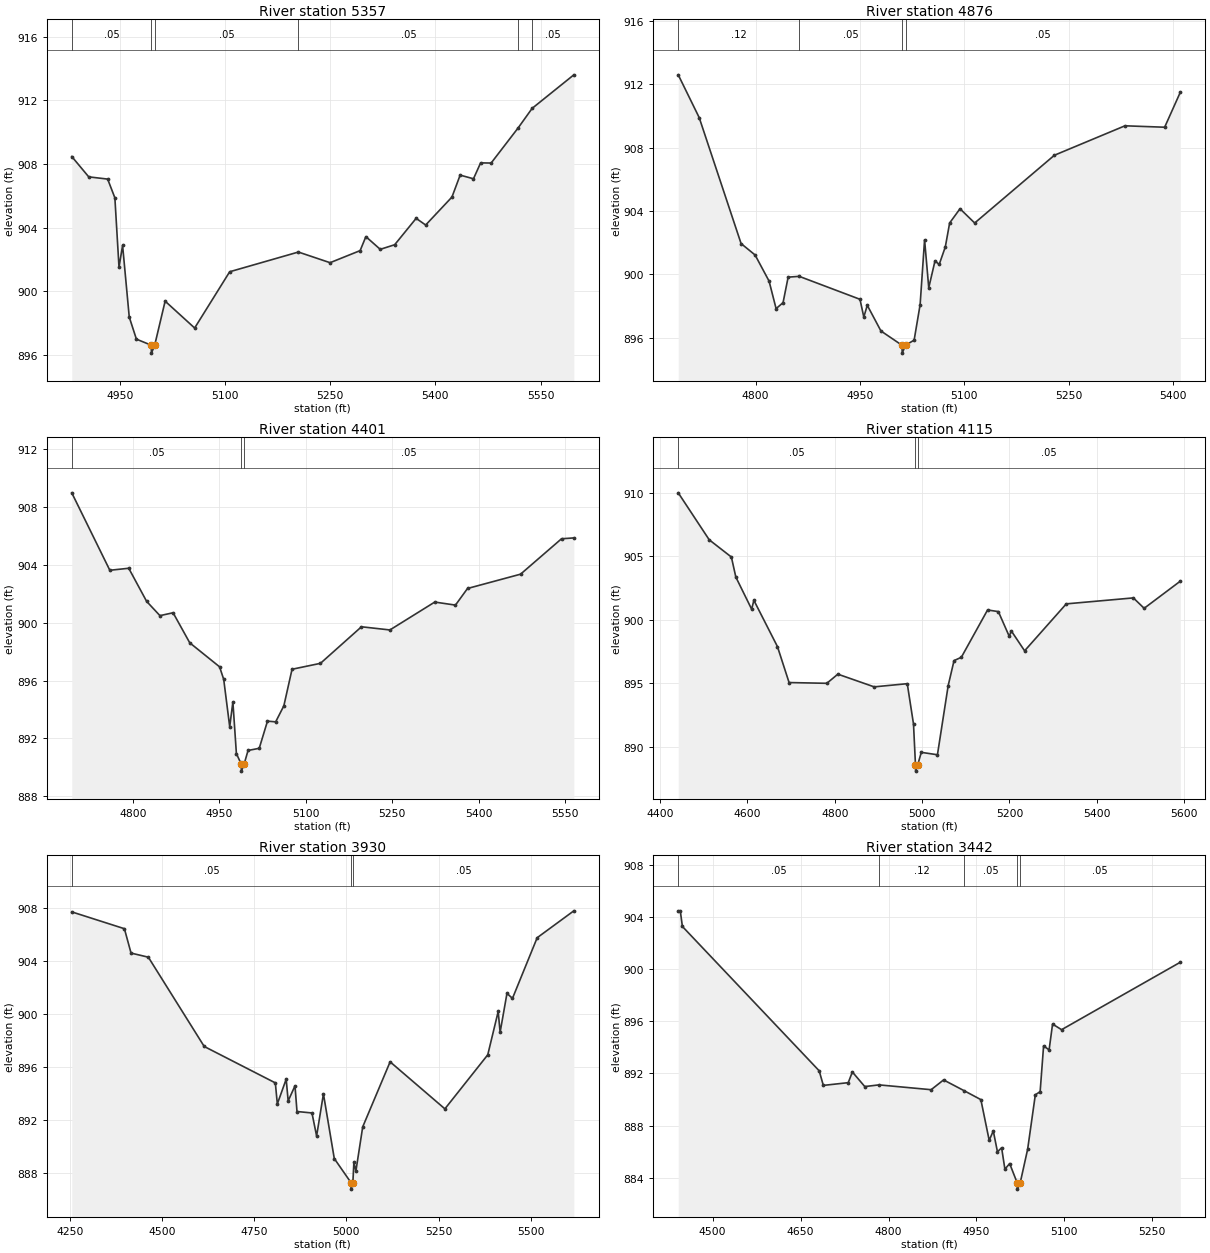
Type RM Length L Ch R = 1,5357,481,481,481
BEGIN DESCRIPTION:
FRENCH JOHN CREEK 10.0
END DESCRIPTION:
XS GIS Cut Line= 3
      2879455.65     10228803.10      2879339.75     10228777.00
      2878755.71     10228903.11
#Sta/Elev= 30
  4881.2  908.47  4905.4  907.19  4932.4  907.05  4942.7  905.87  4948.6  901.50
  4953.7  902.88  4963.2  898.37  4973.4  896.98  4994.5  896.60  4994.9  896.10
  4999.5  896.60  5014.4  899.37  5056.5  897.68  5106.5  901.22  5204.5  902.46
  5249.7  901.79  5292.6  902.55  5300.8  903.43  5321.3  902.63  5341.9  902.92
  5372.5  904.58  5386.1  904.16  5423.6  905.92  5435.3  907.30  5454.3  907.07
  5464.5  908.07  5479.5  908.06  5518.2  910.28  5538.0  911.50  5597.5  913.61
#Mann=6,-1,0
  4881.2    0.05       0  4994.5    0.07       0  4999.5    0.05       0
  5204.5    0.05       0  5518.2    0.12       0  5538.0    0.05       0
Bank Sta=4994.5,4999.5
Exp/Cntr=0.3,0.1

Type RM Length L Ch R = 1,4876,475,475,475
BEGIN DESCRIPTION:
FRENCH JOHN CREEK 9.0
END DESCRIPTION:
XS GIS Cut Line= 3
      2879455.63     10228403.11      2879146.00     10228374.00
      2878805.64     10228603.14
#Sta/Elev= 30
  4689.0  912.61  4719.1  909.91  4779.3  901.95  4799.4  901.23  4819.5  899.58
  4829.6  897.84  4839.6  898.22  4846.9  899.83  4862.8  899.88  4950.1  898.43
  4955.6  897.31  4960.6  898.05  4980.2  896.43  5010.4  895.53  5010.8  895.03
  5015.5  895.53  5027.9  895.85  5036.5  898.09  5042.9  902.19  5048.9  899.16
  5057.9  900.86  5063.9  900.63  5072.7  901.74  5078.9  903.25  5093.8  904.15
  5114.9  903.25  5229.4  907.53  5330.8  909.39  5387.8  909.30  5410.3  911.51
#Mann=4,-1,0
  4689.0    0.12       0  4862.8    0.05       0  5010.4    0.03       0
  5015.5    0.05       0
Bank Sta=5010.4,5015.5
Exp/Cntr=0.3,0.1

Type RM Length L Ch R = 1,4401,286,286,286
BEGIN DESCRIPTION:
FRENCH JOHN CREEK 8.0
END DESCRIPTION:
XS GIS Cut Line= 3
      2879555.72     10228053.13      2879277.25     10227927.00
      2878855.65     10228303.14
#Sta/Elev= 30
  4694.3  908.99  4760.3  903.63  4793.1  903.77  4824.1  901.48  4847.2  900.49
  4870.0  900.69  4898.9  898.61  4950.6  896.95  4957.8  896.08  4968.2  892.80
  4973.7  894.52  4979.8  890.94  4988.1  890.23  4988.5  889.73  4993.3  890.23
  5000.0  891.16  5019.4  891.31  5033.7  893.19  5047.9  893.14  5062.1  894.25
  5076.3  896.78  5125.6  897.19  5196.7  899.72  5246.0  899.50  5323.8  901.43
  5359.7  901.22  5380.6  902.37  5472.6  903.36  5543.6  905.81  5565.0  905.87
#Mann=3,-1,0
  4694.3    0.05       0  4988.1    0.05       0  4993.3    0.05       0
Bank Sta=4988.1,4993.3
Exp/Cntr=0.3,0.1

Type RM Length L Ch R = 1,4115,185,185,185
BEGIN DESCRIPTION:
Mapping XS d29eb1f3
END DESCRIPTION:
XS GIS Cut Line= 3
      2879595.53     10227638.56      2879204.91     10227708.00
      2878501.79     10227977.09
#Sta/Elev= 30
  4441.6  910.00  4512.5  906.30  4563.3  904.94  4573.5  903.36  4609.7  900.83
  4614.8  901.53  4668.8  897.88  4695.4  895.05  4781.8  894.99  4807.1  895.71
  4890.2  894.71  4966.0  894.96  4980.3  891.78  4984.8  888.57  4985.2  888.07
  4990.0  888.57  4998.1  889.55  5035.1  889.36  5059.7  894.81  5073.1  896.78
  5089.8  897.04  5149.9  900.77  5174.6  900.64  5199.3  898.71  5204.6  899.10
  5234.7  897.55  5330.1  901.25  5483.7  901.72  5508.4  900.90  5591.2  903.04
#Mann=3,-1,0
  4441.6    0.05       0  4984.8    0.05       0  4990.0    0.05       0
Bank Sta=4984.8,4990
Exp/Cntr=0.3,0.1

Type RM Length L Ch R = 1,3930,488,488,488
BEGIN DESCRIPTION:
Mapping XS 3c244d55
END DESCRIPTION:
XS GIS Cut Line= 3
      2879647.58     10227326.07      2878849.01     10227655.92
      2878371.61     10227794.80
#Sta/Elev= 30
  4255.6  907.69  4398.3  906.42  4416.3  904.58  4463.2  904.27  4614.7  897.53
  4807.5  894.78  4812.9  893.19  4836.9  895.06  4842.3  893.42  4860.8  894.56
  4866.2  892.62  4906.8  892.51  4919.4  890.77  4937.9  893.95  4967.3  889.07
  5012.4  887.26  5012.8  886.76  5017.7  887.26  5020.5  888.80  5025.9  888.12
  5044.4  891.46  5118.7  896.37  5267.2  892.82  5383.4  896.90  5411.7  900.17
  5416.9  898.60  5435.5  901.54  5450.4  901.16  5517.4  905.74  5616.8  907.77
#Mann=3,-1,0
  4255.6    0.05       0  5012.4    0.05       0  5017.7    0.05       0
Bank Sta=5012.4,5017.7
Exp/Cntr=0.3,0.1

Type RM Length L Ch R = 1,3442,622,622,622
BEGIN DESCRIPTION:
FRENCH JOHN CREEK 6.0
END DESCRIPTION:
XS GIS Cut Line= 3
      2879155.70     10226803.09      2878758.50     10227196.00
      2878505.65     10227353.13
#Sta/Elev= 30
  4441.3  904.46  4444.8  904.46  4448.4  903.26  4681.7  892.20  4688.8  891.08
  4731.3  891.29  4738.3  892.11  4759.5  890.99  4783.7  891.12  4872.7  890.75
  4893.9  891.50  4928.7  890.68  4957.5  889.99  4971.7  886.87  4978.7  887.59
  4985.8  885.99  4992.9  886.30  4998.5  884.66  5006.6  885.09  5019.3  883.63
  5019.7  883.13  5024.7  883.63  5037.3  886.19  5050.4  890.36  5058.6  890.60
  5064.5  894.11  5073.9  893.80  5079.8  895.78  5095.2  895.35  5297.7  900.52
#Mann=5,-1,0
  4441.3    0.05       0  4783.7    0.12       0  4928.7    0.05       0
  5019.3    0.05       0  5024.7    0.05       0
Bank Sta=5019.3,5024.7
Exp/Cntr=0.3,0.1

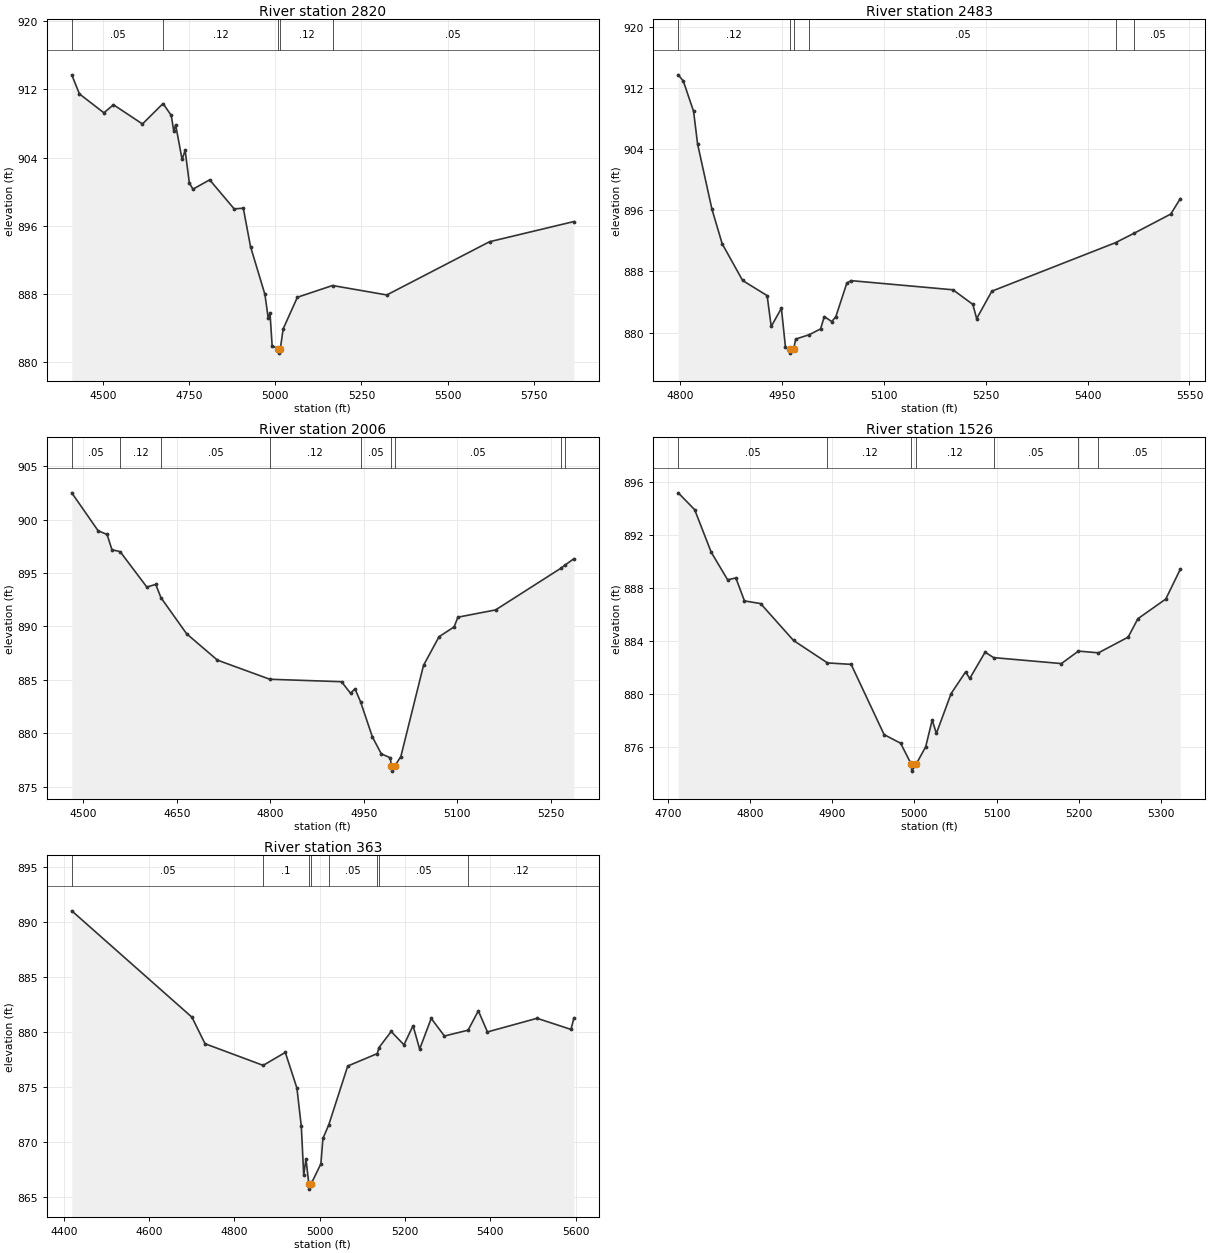
Type RM Length L Ch R = 1,2820,337,337,337
BEGIN DESCRIPTION:
Mapping XS c4a89751
END DESCRIPTION:
XS GIS Cut Line= 3
      2879141.84     10226451.67      2878454.33     10226660.00
      2878051.55     10227278.06
#Sta/Elev= 30
  4410.0  913.72  4432.2  911.48  4503.2  909.26  4530.9  910.21  4615.0  907.95
  4674.7  910.35  4698.6  908.95  4705.9  907.07  4711.2  907.86  4729.9  903.79
  4738.8  904.85  4750.8  901.05  4761.3  900.29  4809.9  901.39  4881.0  897.98
  4907.5  898.06  4928.4  893.55  4970.2  887.93  4979.7  885.15  4984.9  885.75
  4991.1  881.90  5009.3  881.54  5009.7  881.04  5014.8  881.54  5023.1  883.89
  5064.3  887.60  5166.3  888.98  5323.6  887.87  5621.5  894.12  5866.1  896.49
#Mann=5,-1,0
  4410.0    0.05       0  4674.7    0.12       0  5009.3    0.07       0
  5014.8    0.12       0  5166.3    0.05       0
Bank Sta=5009.3,5014.8
Exp/Cntr=0.3,0.1

Type RM Length L Ch R = 1,2483,477,477,477
BEGIN DESCRIPTION:
FRENCH JOHN CREEK 4.0
END DESCRIPTION:
XS GIS Cut Line= 3
      2878505.65     10226353.13      2878336.50     10226465.00
      2877855.72     10226703.09
#Sta/Elev= 30
  4797.2  913.74  4804.7  912.92  4819.8  908.96  4825.7  904.68  4846.8  896.17
  4861.9  891.63  4892.0  886.82  4928.1  884.84  4934.1  880.80  4949.1  883.18
  4955.1  878.07  4961.5  877.81  4961.9  877.31  4967.0  877.81  4970.2  879.15
  4990.0  879.72  5006.8  880.48  5012.3  882.10  5023.2  881.44  5029.2  882.07
  5045.5  886.49  5051.6  886.80  5201.8  885.60  5231.0  883.69  5236.6  881.83
  5259.0  885.42  5441.1  891.77  5469.0  893.03  5522.5  895.52  5536.5  897.54
#Mann=6,-1,0
  4797.2    0.12       0  4961.5    0.05       0  4967.0    0.12       0
  4990.0    0.05       0  5441.1    0.12       0  5469.0    0.05       0
Bank Sta=4961.5,4967
Exp/Cntr=0.3,0.1

Type RM Length L Ch R = 1,2006,480,480,480
BEGIN DESCRIPTION:
FRENCH JOHN CREEK 3.0
END DESCRIPTION:
XS GIS Cut Line= 3
      2878305.69     10226003.11      2877906.50     10226334.00
      2877805.68     10226603.13
#Sta/Elev= 30
  4481.5  902.51  4523.8  898.96  4538.2  898.61  4546.0  897.18  4559.1  897.01
  4602.0  893.69  4616.3  893.94  4624.6  892.70  4665.8  889.32  4715.3  886.85
  4799.4  885.06  4914.5  884.83  4928.9  883.75  4936.1  884.16  4945.0  882.96
  4964.0  879.67  4978.3  878.08  4992.7  877.71  4994.5  876.96  4994.9  876.46
  5000.1  876.96  5009.7  877.82  5046.1  886.36  5071.0  889.04  5095.2  889.96
  5101.3  890.87  5161.8  891.55  5266.3  895.44  5274.0  895.78  5287.4  896.34
#Mann=9,-1,0
  4481.5    0.05       0  4559.1    0.12       0  4624.6    0.05       0
  4799.4    0.12       0  4945.0    0.05       0  4994.5    0.05       0
  5000.1    0.05       0  5266.3    0.12       0  5274.0    0.05       0
Bank Sta=4994.5,5000.1
Exp/Cntr=0.3,0.1

Type RM Length L Ch R = 1,1526,1163,1163,1163
BEGIN DESCRIPTION:
FRENCH JOHN CREEK 2.0
END DESCRIPTION:
XS GIS Cut Line= 3
      2878055.68     10225903.11      2877769.00     10225922.00
      2877455.73     10226003.10
#Sta/Elev= 30
  4712.7  895.15  4732.7  893.88  4752.8  890.68  4772.8  888.60  4782.8  888.74
  4793.3  887.01  4812.9  886.81  4853.0  884.03  4894.3  882.34  4923.1  882.23
  4963.2  876.94  4983.3  876.29  4996.4  874.69  4996.8  874.19  5002.0  874.69
  5013.8  876.03  5021.7  878.04  5026.8  877.03  5044.7  880.03  5062.3  881.66
  5067.4  881.17  5086.1  883.15  5096.4  882.74  5178.9  882.29  5199.6  883.23
  5224.0  883.10  5260.1  884.28  5272.0  885.67  5305.9  887.15  5323.6  889.40
#Mann=7,-1,0
  4712.7    0.05       0  4894.3    0.12       0  4996.4    0.07       0
  5002.0    0.12       0  5096.4    0.05       0  5199.6    0.12       0
  5224.0    0.05       0
Bank Sta=4996.4,5002
Exp/Cntr=0.3,0.1

Type RM Length L Ch R = 1,363,0,0,0
BEGIN DESCRIPTION:
FRENCH JOHN CREEK 1.0
END DESCRIPTION:
XS GIS Cut Line= 3
      2878050.43     10225208.01      2877483.50     10225080.00
      2877174.23     10225589.01
#Sta/Elev= 30
  4418.8  891.06  4700.5  881.39  4731.1  878.98  4867.4  877.01  4919.3  878.19
  4946.5  874.95  4956.8  871.47  4962.5  867.02  4967.7  868.51  4974.4  866.26
  4974.9  865.76  4980.1  866.26  5002.7  868.06  5007.5  870.37  5021.2  871.61
  5065.6  876.95  5134.8  878.08  5138.7  878.62  5167.5  880.09  5197.4  878.88
  5218.7  880.62  5234.2  878.49  5261.3  881.28  5292.3  879.68  5347.7  880.21
  5371.8  881.97  5393.1  880.05  5509.4  881.29  5588.9  880.28  5595.6  881.31
#Mann=8,-1,0
  4418.8    0.05       0  4867.4     0.1       0  4974.4    0.07       0
  4980.1     0.1       0  5021.2    0.05       0  5134.8    0.12       0
  5138.7    0.05       0  5347.7    0.12       0
Bank Sta=4974.4,4980.1
Exp/Cntr=0.3,0.1

Chan Stop Cuts=-1