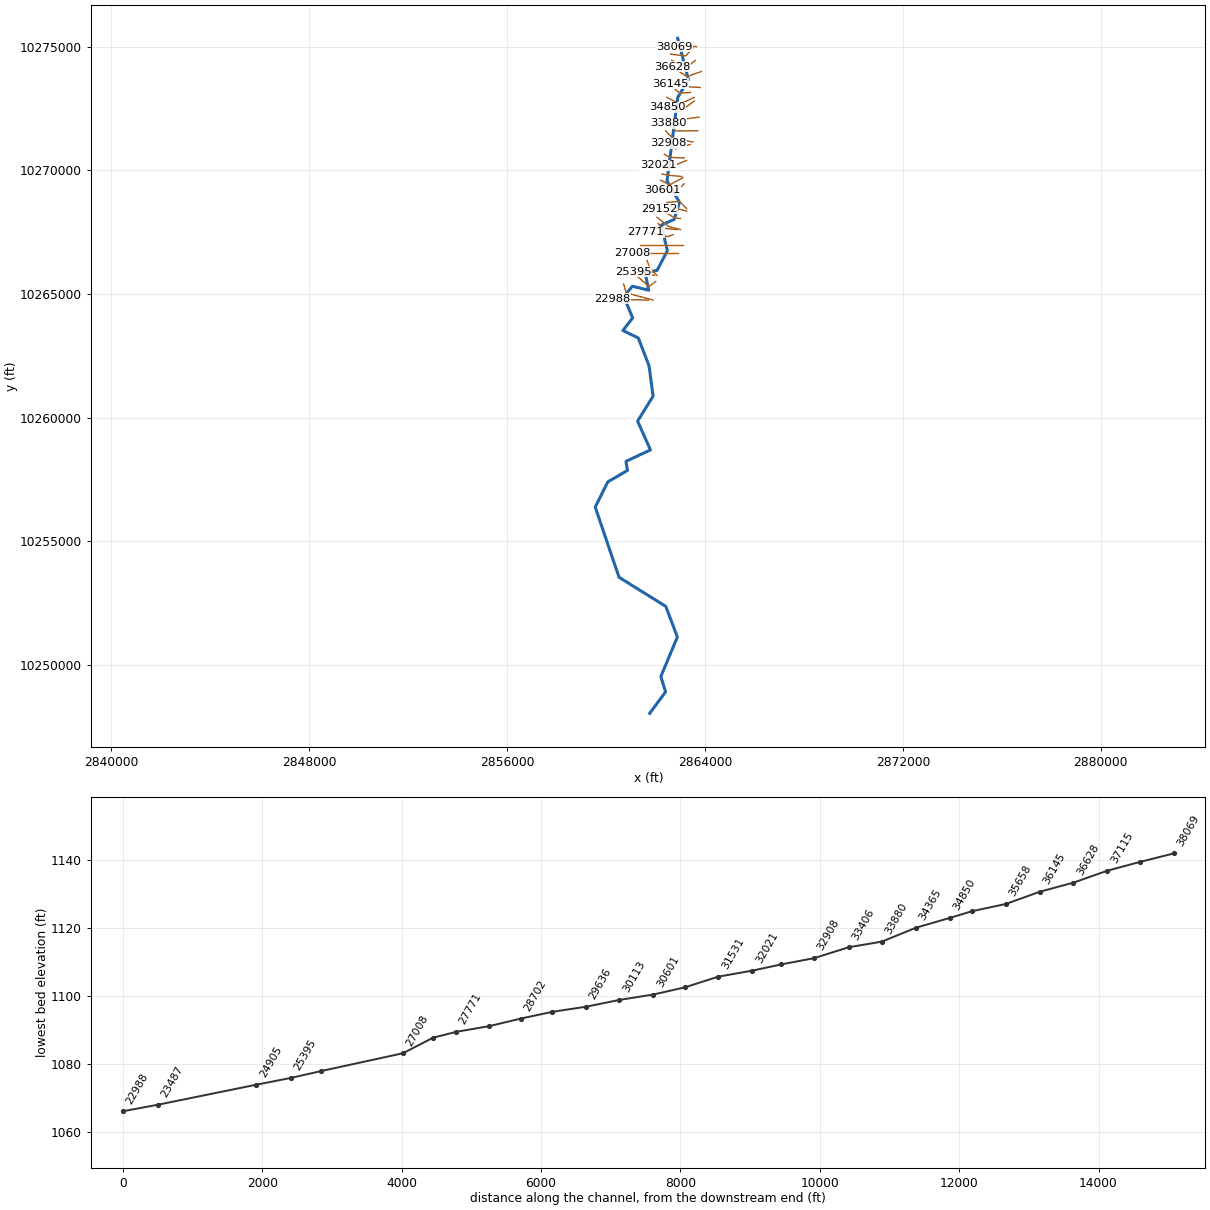
--- HARRIS BRANCH.prj (project) ---

Proj Title=HARRIS BRANCH Base Level Engineering
Current Plan=p01
Default Exp/Contr=0.3,0.1
English Units
Geom File=g01
Flow File=f01
Plan File=p01
Y Axis Title=Elevation
X Axis Title(PF)=Main Channel Distance
X Axis Title(XS)=Station
BEGIN DESCRIPTION:
HARRIS BRANCH
END DESCRIPTION:
DSS Export Rating Curves= 0
DSS Export Rating Curve Sorted= 0
DSS Export Volume Flow Curves= 0
DXF OffsetX= 0
DXF OffsetY= 0
DXF ScaleX= 1
DXF ScaleY= 10

--- HARRIS BRANCH.p01 (plan) ---

Plan Title=Multiple Run
Short Identifier=Multiple
Geom File=g01
Flow File=f01
Subcritical Flow
K Sum by GR= 0
Std Step Tol= 0.01
Critical Tol= 0.01
Num of Std Step Trials= 20
Max Error Tol= 0.3
Flow Tol Ratio= 0.001
Split Flow NTrial= 30
Split Flow Tol= 0.02
Split Flow Ratio= 0.02
Log Output Level= 0
Friction Slope Method= 1
Unsteady Friction Slope Method= 2
Unsteady Bridges Friction Slope Method= 1
Parabolic Critical Depth
Global Vel Dist=  1 , 1 , 1
Global Log Level= 0
CheckData=True
Encroach Param= -1, 0, 0, 0
BEGIN DESCRIPTION:
Multiple Run
END DESCRIPTION:

--- HARRIS BRANCH.f01 (steady flow) ---

Flow Title=Multiple
Number of Profiles=7
Profile Names=10-year,25-year,50-year,1pct_min,100-year,1pct_plu,500-year
River Rch & RM= HARRIS BRANCH,Reach-1,38069
     567     945    1040     590    1177    2348    1571
River Rch & RM= HARRIS BRANCH,Reach-1,23487
     997    1734    1907    1042    2266    4928    3041
River Rch & RM= HARRIS BRANCH,Reach-1,9661
    1233    2165    2304    1440    3105    6696    4166
River Rch & RM= HARRIS BRANCH,Reach-1,8354
    1522    2714    2963    1822    4034    8931    5430
Boundary for River Rch & Prof#=HARRIS BRANCH,Reach-1,1
Up Type=0
Dn Type=3
Dn Slope=0.005
Boundary for River Rch & Prof#=HARRIS BRANCH,Reach-1,2
Up Type=0
Dn Type=3
Dn Slope=0.005
Boundary for River Rch & Prof#=HARRIS BRANCH,Reach-1,3
Up Type=0
Dn Type=3
Dn Slope=0.005
Boundary for River Rch & Prof#=HARRIS BRANCH,Reach-1,4
Up Type=0
Dn Type=3
Dn Slope=0.005
Boundary for River Rch & Prof#=HARRIS BRANCH,Reach-1,5
Up Type=0
Dn Type=3
Dn Slope=0.005
Boundary for River Rch & Prof#=HARRIS BRANCH,Reach-1,6
Up Type=0
Dn Type=3
Dn Slope=0.005
Boundary for River Rch & Prof#=HARRIS BRANCH,Reach-1,7
Up Type=0
Dn Type=3
Dn Slope=0.005

--- HARRIS BRANCH.g01 (geometry) ---

Geom Title=Existing Conditions
Program Version=4.10

River Reach=HARRIS BRANCH   ,Reach-1
Reach XY= 30
      2862893.25       10275343.       2863329.5       10273677.
        2862895.       10272954.      2862462.25       10269568.
        2862965.       10268709.        2862752.       10268017.
       2862231.5       10267789.        2862476.       10266753.
      2862059.75       10265951.      2861575.25       10265866.
        2861722.       10265151.      2861065.75       10265313.
      2860712.75       10264904.        2861072.       10264029.
      2860678.25       10263523.      2861303.75       10263217.
        2861734.       10262097.       2861899.5       10260865.
      2861273.25       10259857.       2861792.5       10258691.
      2860800.25       10258226.        2860865.       10257863.
      2860066.75       10257395.       2859559.5       10256376.
        2860522.       10253538.      2862412.75       10252360.
        2862880.       10251120.        2862212.       10249519.
      2862404.25       10248901.      2861761.25       10248031.

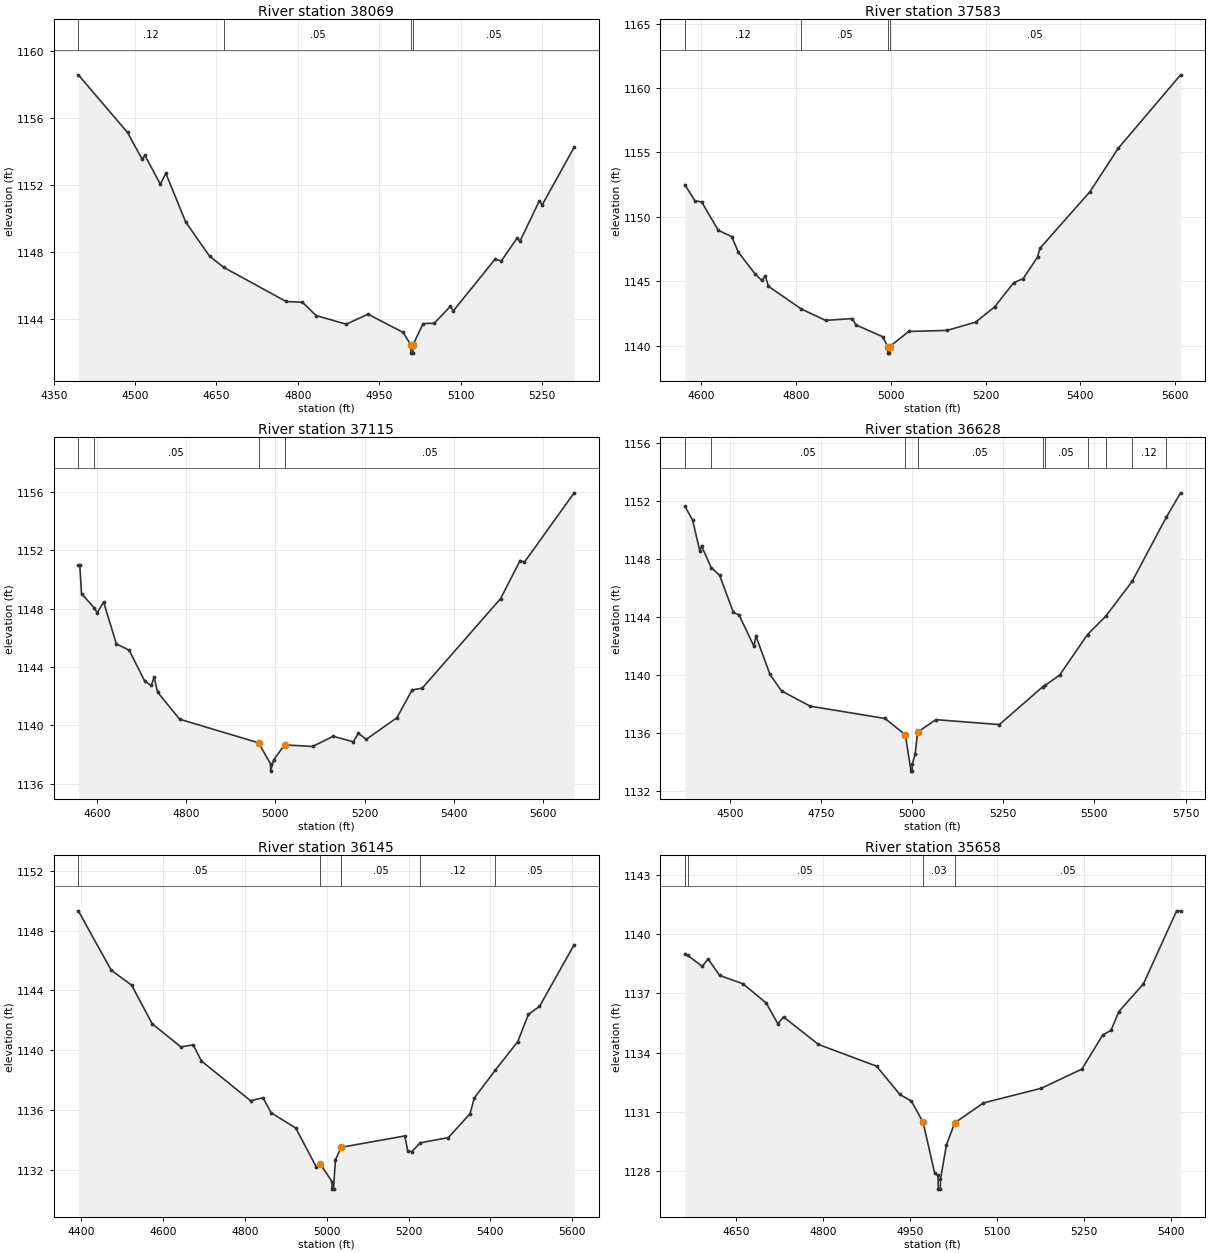
Type RM Length L Ch R = 1 ,38069   ,486,486,486
BEGIN DESCRIPTION:
HARRIS BRANCH 74.0
END DESCRIPTION:
XS GIS Cut Line= 3
      2863655.67     10275003.11      2863055.75       10275079.
       2862755.7     10275003.11
#Sta/Elev= 30
  4395.3 1158.59    4486 1155.14    4513 1153.54    4518 1153.77  4546.5 1152.05
  4556.6  1152.7  4593.2 1149.79  4637.2 1147.74  4663.5 1147.07  4778.3 1145.03
  4808.6 1144.98  4833.7 1144.19  4889.2 1143.67  4929.5 1144.27    4994 1143.18
  5008.4 1142.44  5008.6 1141.94  5012.1 1141.94  5012.4 1142.44    5031 1143.71
  5051.6 1143.73  5081.3 1144.74  5086.5 1144.46  5163.4 1147.55  5175.4 1147.46
  5204.4 1148.83  5209.5 1148.63  5245.4 1151.06  5250.6 1150.81  5309.5 1154.26
#Mann= 4 ,-1 , 0
  4395.3     .12       0  4663.5     .05       0  5008.4     .03       0
  5012.4     .05       0
Bank Sta=5008.4,5012.4
XS Rating Curve= 0 ,0
Exp/Cntr=0.3,0.1

Type RM Length L Ch R = 1 ,37583   ,468,468,468
BEGIN DESCRIPTION:
HARRIS BRANCH 73.0
END DESCRIPTION:
XS GIS Cut Line= 3
      2863505.67     10274953.09        2863213.       10274631.
      2862605.67     10274703.11
#Sta/Elev= 30
  4564.8 1152.51  4586.1 1151.25  4600.3 1151.17  4635.4 1148.97  4663.8 1148.47
    4678 1147.26  4713.4 1145.57  4727.3 1145.08  4734.7 1145.43  4741.5 1144.62
  4810.5 1142.87    4862 1141.98  4918.5 1142.12    4926 1141.63  4982.7 1140.71
  4993.2 1139.94  4993.4 1139.44  4996.9 1139.44  4997.2 1139.94  5037.6 1141.12
  5118.1  1141.2  5178.6 1141.84  5218.8 1143.02  5259.1  1144.9  5279.3 1145.22
  5309.5 1146.89  5314.6 1147.57  5420.2 1151.96    5480 1155.33  5611.6 1161.02
#Mann= 4 ,-1 , 0
  4564.8     .12       0  4810.5     .05       0  4993.2     .03       0
  4997.2     .05       0
Bank Sta=4993.2,4997.2
XS Rating Curve= 0 ,0
Exp/Cntr=0.3,0.1

Type RM Length L Ch R = 1 ,37115   ,487,487,487
BEGIN DESCRIPTION:
HARRIS BRANCH 72.0
END DESCRIPTION:
XS GIS Cut Line= 3
      2863605.71     10274453.13      2863264.25       10274172.
      2862655.64     10274453.13
#Sta/Elev= 30
  4557.7 1150.97    4561 1150.97  4564.9 1149.04  4592.8 1148.08  4600.1 1147.72
  4614.4 1148.47  4643.1 1145.59  4671.8 1145.16  4706.9 1143.03  4721.3 1142.75
  4727.8 1143.31  4735.6 1142.28  4785.1 1140.43  4962.3 1138.81    4989 1137.37
  4989.3 1136.87  4995.8 1137.63  5020.5 1138.67  5083.6 1138.56  5129.5 1139.26
  5174.7 1138.88  5186.3 1139.46  5203.8 1139.05  5272.6 1140.53  5306.8 1142.44
  5329.5 1142.56  5505.1 1148.69  5549.2 1151.31  5558.9  1151.2  5670.4 1155.95
#Mann= 4 ,-1 , 0
  4557.7     .12       0  4592.8     .05       0  4962.3     .03       0
  5020.5     .05       0
Bank Sta=4962.3,5020.5
XS Rating Curve= 0 ,0
Exp/Cntr=0.3,0.1

Type RM Length L Ch R = 1 ,36628   ,483,483,483
BEGIN DESCRIPTION:
HARRIS BRANCH 71.0
END DESCRIPTION:
XS GIS Cut Line= 3
      2863855.64      10274003.1      2863268.25       10273794.
       2862655.7      10274203.1
#Sta/Elev= 30
  4376.5 1151.63  4397.7 1150.69  4417.4 1148.57  4422.7 1148.87  4448.8  1147.4
    4472 1146.86  4509.9  1144.3  4525.1 1144.14  4566.2 1141.97  4571.6 1142.67
    4610 1140.04  4641.8 1138.89  4720.4 1137.84  4925.6 1136.99  4981.5 1135.86
    4997 1133.36  5000.5 1133.36  5000.7 1133.86  5008.3 1134.52  5015.1 1136.05
  5065.3 1136.91  5239.5 1136.57  5358.9 1139.19  5364.6 1139.27  5404.7 1139.98
  5481.2 1142.78  5530.8 1144.03  5603.5 1146.44  5697.1 1150.86  5736.6 1152.55
#Mann= 10 ,-1 , 0
  4376.5     .12       0  4448.8     .05       0  4981.5     .03       0
  5015.1     .05       0  5358.9     .12       0  5364.6     .05       0
  5481.2     .12       0  5530.8     .05       0  5603.5     .12       0
  5697.1     .05       0
Bank Sta=4981.5,5015.1
XS Rating Curve= 0 ,0
Exp/Cntr=0.3,0.1

Type RM Length L Ch R = 1 ,36145   ,487,487,487
BEGIN DESCRIPTION:
HARRIS BRANCH 70.0
END DESCRIPTION:
XS GIS Cut Line= 3
      2863805.72     10273353.11       2863200.5       10273394.
      2862605.72      10273503.1
#Sta/Elev= 30
  4393.4 1149.32  4473.6 1145.35  4523.7 1144.34  4573.8 1141.76    4644 1140.21
  4674.1 1140.35  4694.1 1139.27  4814.4  1136.6  4844.5 1136.81  4864.5  1135.8
  4924.6 1134.78  4974.8 1132.17  4984.8 1132.37  5013.1 1131.19  5013.3 1130.69
  5016.8 1130.69  5021.5 1132.65  5035.4 1133.49    5191 1134.25  5198.1 1133.24
  5208.2  1133.2  5228.7 1133.79  5297.3 1134.14  5350.4 1135.74  5360.7 1136.79
  5412.5 1138.67  5466.8 1140.56  5492.9 1142.39    5520 1142.92  5604.7 1147.05
#Mann= 5 ,-1 , 0
  4393.4     .05       0  4984.8     .03       0  5035.4     .05       0
  5228.7     .12       0  5412.5     .05       0
Bank Sta=4984.8,5035.4
XS Rating Curve= 0 ,0
Exp/Cntr=0.3,0.1

Type RM Length L Ch R = 1 ,35658   ,487,487,487
BEGIN DESCRIPTION:
HARRIS BRANCH 69.0
END DESCRIPTION:
XS GIS Cut Line= 3
      2863405.73     10273153.11      2862967.75       10273128.
       2862655.7      10273403.1
#Sta/Elev= 30
  4561.3    1139    4566 1138.93  4591.4 1138.37  4601.4 1138.75  4621.4 1137.91
  4661.5 1137.49  4701.6 1136.52  4721.6 1135.47  4731.6 1135.81  4791.7 1134.42
  4891.9 1133.32    4932 1131.89    4952 1131.55    4972 1130.49  4992.1  1127.9
  4997.6 1127.79  4998.3  1127.1  5001.8  1127.1    5002  1127.6  5012.4 1129.35
  5026.6 1130.45  5075.9 1131.46  5175.5  1132.2  5245.7 1133.17  5281.8  1134.9
    5296 1135.13  5309.4 1136.08    5352 1137.49  5408.9 1141.17    5416 1141.18
#Mann= 4 ,-1 , 0
  4561.3     .12       0    4566     .05       0    4972     .03       0
  5026.6     .05       0
Bank Sta=4972,5026.6
XS Rating Curve= 0 ,0
Exp/Cntr=0.3,0.1

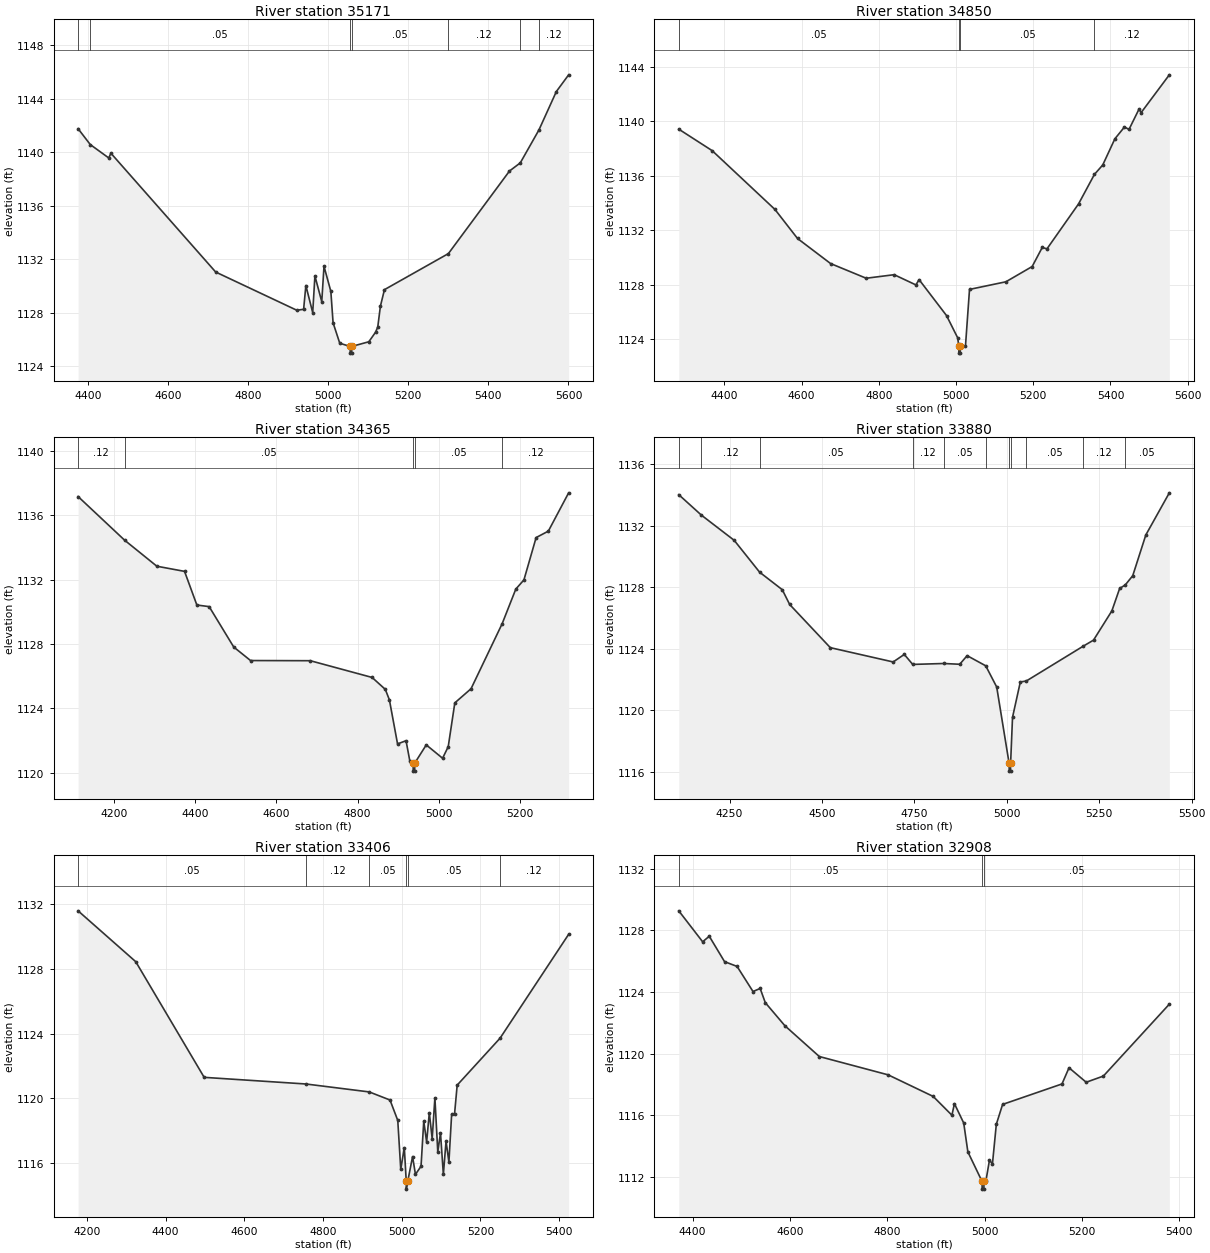
Type RM Length L Ch R = 1 ,35171   ,321,321,321
BEGIN DESCRIPTION:
HARRIS BRANCH 68.0
END DESCRIPTION:
XS GIS Cut Line= 3
      2863555.72     10272953.13        2862992.       10272683.
      2862455.68     10272953.11
#Sta/Elev= 30
  4374.9 1141.76  4405.4 1140.57  4451.5 1139.57    4457 1139.92  4718.7 1131.03
  4921.3 1128.17  4938.4 1128.24    4944 1130.02  4961.1 1127.99  4966.6 1130.74
  4983.7 1128.81  4989.3 1131.46  5006.4 1129.58    5012 1127.23  5028.7  1125.7
  5054.6 1125.46  5054.9 1124.96  5058.4 1124.96  5058.6 1125.46  5101.3 1125.81
    5118 1126.52  5123.6 1126.91  5130.2 1128.47  5140.3 1129.71  5300.1 1132.41
  5452.7 1138.59  5479.7  1139.2  5526.2 1141.66  5569.8 1144.54  5600.5 1145.79
#Mann= 7 ,-1 , 0
  4374.9     .12       0  4405.4     .05       0  5054.6     .03       0
  5058.6     .05       0  5300.1     .12       0  5479.7     .05       0
  5526.2     .12       0
Bank Sta=5054.6,5058.6
XS Rating Curve= 0 ,0
Exp/Cntr=0.3,0.1

Type RM Length L Ch R = 1 ,34850   ,485,485,485
BEGIN DESCRIPTION:
HARRIS BRANCH 67.0
END DESCRIPTION:
XS GIS Cut Line= 3
      2863555.67      10272803.1      2862978.75       10272375.
      2862455.65     10272553.12
#Sta/Elev= 30
  4281.6 1139.43  4368.2 1137.85  4530.9 1133.53  4589.3  1131.4  4674.9 1129.56
  4767.2 1128.48  4839.7 1128.74    4896 1127.99  4904.2 1128.38  4975.3 1125.74
  5004.3  1124.1  5007.1 1123.48  5007.3 1122.98  5010.8 1122.98  5011.1 1123.48
  5024.4 1123.49  5034.9 1127.66  5129.2 1128.22  5197.2 1129.34  5223.3 1130.74
  5235.6 1130.64  5317.4 1133.94  5358.6 1136.11  5380.1  1136.8  5411.5 1138.72
  5436.4 1139.59  5448.1 1139.41  5474.2 1140.91  5479.4 1140.64  5552.6 1143.42
#Mann= 4 ,-1 , 0
  4281.6     .05       0  5007.1     .03       0  5011.1     .05       0
  5358.6     .12       0
Bank Sta=5007.1,5011.1
XS Rating Curve= 0 ,0
Exp/Cntr=0.3,0.1

Type RM Length L Ch R = 1 ,34365   ,485,485,485
BEGIN DESCRIPTION:
HARRIS BRANCH 66.0
END DESCRIPTION:
XS GIS Cut Line= 3
      2863755.68     10272153.11        2862875.       10272037.
      2862555.71     10272053.11
#Sta/Elev= 30
  4111.7 1137.16  4226.2 1134.45  4305.7 1132.83  4373.9 1132.51  4404.2 1130.42
  4434.5 1130.32    4495 1127.81  4536.4 1126.97  4683.5 1126.96  4835.7 1125.92
  4868.2 1125.18  4878.3 1124.53  4898.4 1121.79  4919.3 1121.99  4928.7 1120.72
  4936.8  1120.6    4937  1120.1  4940.5  1120.1  4940.8  1120.6  4969.1 1121.73
  5009.3  1120.9  5023.2 1121.62  5039.4 1124.34  5079.4 1125.22    5156 1129.26
  5189.6 1131.41  5209.6 1131.98  5239.6 1134.61  5269.7 1135.01  5319.7 1137.39
#Mann= 5 ,-1 , 0
  4111.7     .12       0  4226.2     .05       0  4936.8     .03       0
  4940.8     .05       0    5156     .12       0
Bank Sta=4936.8,4940.8
XS Rating Curve= 0 ,0
Exp/Cntr=0.3,0.1

Type RM Length L Ch R = 1 ,33880   ,474,474,474
BEGIN DESCRIPTION:
HARRIS BRANCH 65.0
END DESCRIPTION:
XS GIS Cut Line= 3
       2863705.7     10271603.11      2862818.25       10271594.
      2862505.68     10271903.11
#Sta/Elev= 30
  4112.5 1134.02  4173.7 1132.69  4262.5 1131.05  4331.2 1128.98  4392.5 1127.84
  4412.5 1126.88  4522.5 1124.07  4692.5 1123.14  4722.6 1123.63  4745.4 1122.98
  4829.2 1123.04  4872.6 1122.99  4892.6 1123.55  4942.9 1122.89  4972.6 1121.51
  5006.2 1116.54  5006.5 1116.04    5010 1116.04  5010.2 1116.54  5015.4 1119.54
  5036.5 1121.84  5052.6  1121.9  5206.2 1124.16  5234.5 1124.56  5284.1 1126.46
  5305.2 1127.92  5320.4 1128.15  5340.6 1128.75    5376  1131.4  5439.6 1134.14
#Mann= 11 ,-1 , 0
  4112.5     .05       0  4173.7     .12       0  4331.2     .05       0
  4745.4     .12       0  4829.2     .05       0  4942.9     .12       0
  5006.2     .07       0  5010.2     .12       0  5052.6     .05       0
  5206.2     .12       0  5320.4     .05       0
Bank Sta=5006.2,5010.2
XS Rating Curve= 0 ,0
Exp/Cntr=0.3,0.1

Type RM Length L Ch R = 1 ,33406   ,498,498,498
BEGIN DESCRIPTION:
HARRIS BRANCH 64.0
END DESCRIPTION:
XS GIS Cut Line= 3
      2863505.69     10271153.11      2862695.75       10271294.
      2862405.68     10271603.11
#Sta/Elev= 30
  4177.9 1131.58  4324.4 1128.44  4498.2  1121.3  4756.8 1120.89  4917.5  1120.4
  4970.2  1119.9  4989.9 1118.64  4997.5 1115.62  5006.5 1116.96  5011.4  1114.9
  5011.6  1114.4  5015.4  1114.9  5027.5 1116.41  5034.8 1115.31    5049 1115.81
  5055.9  1118.6  5063.2 1117.31    5070 1119.11  5077.3 1117.52  5084.2 1120.04
  5091.5  1116.7  5098.4 1117.86  5105.7 1115.31  5112.5 1117.36  5119.8 1116.07
  5126.7 1119.01    5134 1119.01  5140.8 1120.82  5249.8 1123.72  5423.9 1130.13
#Mann= 6 ,-1 , 0
  4177.9     .05       0  4756.8     .12       0  4917.5     .05       0
  5011.4     .05       0  5015.4     .05       0  5249.8     .12       0
Bank Sta=5011.4,5015.4
XS Rating Curve= 0 ,0
Exp/Cntr=0.3,0.1

Type RM Length L Ch R = 1 ,32908   ,474,474,474
BEGIN DESCRIPTION:
HARRIS BRANCH 63.0
END DESCRIPTION:
XS GIS Cut Line= 3
      2863405.68     10271053.11      2862804.75       10270869.
      2862505.68     10271103.11
#Sta/Elev= 30
  4371.5 1129.27  4420.6 1127.26  4434.2 1127.62  4465.6 1125.97  4491.4 1125.66
  4524.1 1124.03  4538.8 1124.23  4549.3 1123.31  4589.6 1121.81  4660.4 1119.81
  4801.9 1118.62  4894.4 1117.22  4932.9    1116  4938.1 1116.75  4957.2 1115.49
  4965.7 1113.62  4994.9  1111.7  4995.1  1111.2  4998.6  1111.2  4998.9  1111.7
  5002.6  1111.7    5010 1113.06  5016.3 1112.86  5024.2 1115.41  5037.1  1116.7
  5159.2 1118.03  5173.6 1119.08  5208.9 1118.14  5244.2 1118.54  5379.8 1123.21
#Mann= 3 ,-1 , 0
  4371.5     .05       0  4994.9     .03       0  4998.9     .05       0
Bank Sta=4994.9,4998.9
XS Rating Curve= 0 ,0
Exp/Cntr=0.3,0.1

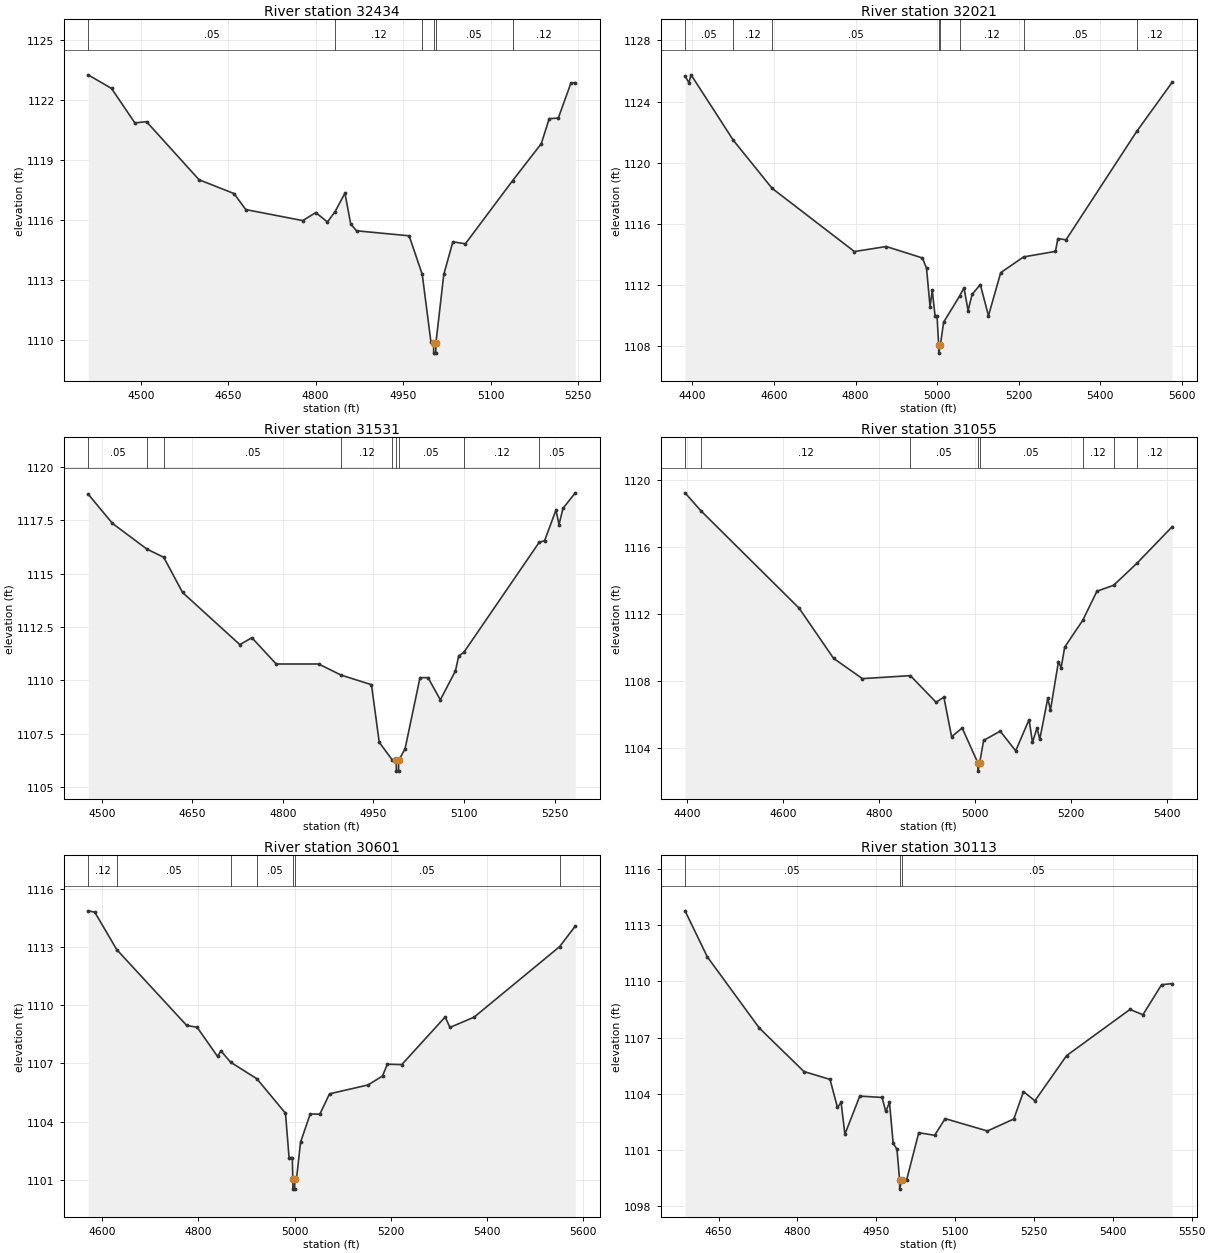
Type RM Length L Ch R = 1 ,32434   ,413,413,413
BEGIN DESCRIPTION:
HARRIS BRANCH 62.0
END DESCRIPTION:
XS GIS Cut Line= 3
      2863155.72     10270503.11        2862566.       10270527.
      2862355.71      10270653.1
#Sta/Elev= 30
  4409.8 1123.24  4449.9 1122.56  4489.9 1120.84  4509.9  1120.9    4600    1118
    4660 1117.31  4680.1 1116.51  4777.8 1115.96  4800.2 1116.36  4820.2 1115.89
  4833.3 1116.41  4850.2 1117.33  4860.2 1115.78  4870.2 1115.45  4960.3  1115.2
  4982.8 1113.27  4997.7 1109.89  5002.2 1109.84  5002.4 1109.34  5005.9 1109.34
  5006.2 1109.84  5019.7 1113.27  5035.3  1114.9  5056.7  1114.8  5137.6 1117.95
  5186.9  1119.8  5200.5 1121.05  5216.1 1121.08  5237.5 1122.81  5245.2 1122.85
#Mann= 6 ,-1 , 0
  4409.8     .05       0  4833.3     .12       0  4982.8     .05       0
  5002.2     .05       0  5006.2     .05       0  5137.6     .12       0
Bank Sta=5002.2,5006.2
XS Rating Curve= 0 ,0
Exp/Cntr=0.3,0.1

Type RM Length L Ch R = 1 ,32021   ,490,490,490
BEGIN DESCRIPTION:
HARRIS BRANCH 61.0
END DESCRIPTION:
XS GIS Cut Line= 3
      2863255.64     10270403.09      2862681.75       10270173.
      2862105.64     10270203.11
#Sta/Elev= 30
  4381.7 1125.68  4391.1 1125.23  4396.5 1125.75  4500.4 1121.46  4595.3 1118.32
  4797.3 1114.18  4875.3 1114.51  4964.1 1113.76  4974.2 1113.09  4982.9 1110.57
  4988.3 1111.65  4995.2 1109.96    5000 1109.96  5004.1 1108.03  5004.3 1107.53
  5008.1 1108.03  5016.1 1109.55  5055.2 1111.26  5066.2  1111.8  5076.2 1110.32
  5086.2 1111.38  5106.2 1112.02  5126.2 1109.98  5156.3  1112.8  5212.4 1113.83
  5290.5 1114.19  5296.5 1115.03  5316.5 1114.95  5489.8 1122.04  5576.9 1125.26
#Mann= 8 ,-1 , 0
  4381.7     .05       0  4500.4     .12       0  4595.3     .05       0
  5004.1     .05       0  5008.1     .05       0  5055.2     .12       0
  5212.4     .05       0  5489.8     .12       0
Bank Sta=5004.1,5008.1
XS Rating Curve= 0 ,0
Exp/Cntr=0.3,0.1

Type RM Length L Ch R = 1 ,31531   ,476,476,476
BEGIN DESCRIPTION:
HARRIS BRANCH 60.0
END DESCRIPTION:
XS GIS Cut Line= 3
      2863055.71     10269753.11       2862535.5       10269803.
      2862255.65     10269853.12
#Sta/Elev= 30
  4477.4 1118.73  4517.6 1117.36  4574.4 1116.16  4602.6 1115.77  4633.8 1114.12
  4728.6 1111.68  4748.7    1112  4788.9 1110.77  4859.2 1110.77  4896.4 1110.25
  4946.7  1109.8  4959.6  1107.1  4981.3 1106.27  4987.8 1106.25    4988 1105.75
  4991.5 1105.75  4991.8 1106.25  5002.4  1106.8  5027.1 1110.13  5040.4 1110.13
  5060.8 1109.09  5085.9 1110.45  5091.2 1111.15  5099.6 1111.31  5224.5 1116.47
  5233.5 1116.55  5252.3 1117.98  5257.4  1117.3  5263.9 1118.06  5284.3 1118.79
#Mann= 9 ,-1 , 0
  4477.4     .05       0  4574.4     .12       0  4602.6     .05       0
  4896.4     .12       0  4981.3     .05       0  4987.8     .05       0
  4991.8     .05       0  5099.6     .12       0  5224.5     .05       0
Bank Sta=4987.8,4991.8
XS Rating Curve= 0 ,0
Exp/Cntr=0.3,0.1

Type RM Length L Ch R = 1 ,31055   ,454,454,454
BEGIN DESCRIPTION:
HARRIS BRANCH 59.0
END DESCRIPTION:
XS GIS Cut Line= 3
      2863105.68     10269703.11      2862572.75       10269418.
      2862205.68     10269603.11
#Sta/Elev= 30
  4395.6 1119.21    4429 1118.13  4633.7 1112.33  4705.2 1109.35  4765.4 1108.14
  4865.3 1108.32    4919 1106.73  4935.2 1107.04  4951.3 1104.68  4973.4  1105.2
  5005.9 1103.13  5006.2 1102.63  5009.9 1103.13    5018 1104.46  5052.7 1105.01
  5084.9 1103.84  5112.8  1105.7  5119.9 1104.35  5129.5 1105.21  5135.1 1104.52
  5151.8 1106.97  5157.4 1106.27  5174.1 1109.16  5179.7 1108.79  5187.1 1110.02
  5224.8 1111.62  5254.3 1113.35    5289  1113.7  5337.9 1115.02  5411.1 1117.19
#Mann= 8 ,-1 , 0
  4395.6     .05       0    4429     .12       0  4865.3     .05       0
  5005.9     .05       0  5009.9     .05       0  5224.8     .12       0
    5289     .05       0  5337.9     .12       0
Bank Sta=5005.9,5009.9
XS Rating Curve= 0 ,0
Exp/Cntr=0.3,0.1

Type RM Length L Ch R = 1 ,30601   ,488,488,488
BEGIN DESCRIPTION:
HARRIS BRANCH 58.0
END DESCRIPTION:
XS GIS Cut Line= 3
      2863155.65     10269453.08        2862838.       10269164.
      2862255.71     10269203.11
#Sta/Elev= 30
  4570.5 1114.88  4584.3 1114.81  4629.9 1112.88  4775.5 1108.96  4797.1 1108.87
  4839.7 1107.36  4846.5 1107.65    4867 1107.06  4921.4 1106.21  4980.9 1104.43
  4988.4 1102.14  4995.1 1102.14  4996.2 1101.01  4996.4 1100.51  4999.9 1100.51
  5000.2 1101.01  5003.7 1101.01  5012.3 1102.94  5032.4 1104.39  5052.4 1104.38
  5072.5 1105.43  5152.7 1105.89  5182.7 1106.35  5192.7 1106.96  5222.8 1106.94
    5313  1109.4    5323 1108.86  5373.2 1109.39    5551 1113.03  5583.6 1114.09
#Mann= 7 ,-1 , 0
  4570.5     .12       0  4629.9     .05       0    4867     .12       0
  4921.4     .05       0  4996.2     .05       0  5000.2     .05       0
    5551     .12       0
Bank Sta=4996.2,5000.2
XS Rating Curve= 0 ,0
Exp/Cntr=0.3,0.1

Type RM Length L Ch R = 1 ,30113   ,477,477,477
BEGIN DESCRIPTION:
HARRIS BRANCH 57.0
END DESCRIPTION:
XS GIS Cut Line= 3
      2863255.66     10268453.14       2862966.5       10268749.
      2862455.66     10268703.11
#Sta/Elev= 30
  4586.3 1113.76  4628.6 1111.31  4727.6 1107.51  4812.5 1105.19  4862.1 1104.77
  4876.2 1103.28  4883.2 1103.54  4890.4 1101.85  4918.7 1103.88  4961.1 1103.81
  4968.1 1103.06  4975.2 1103.55  4982.2 1101.36  4989.4 1101.05  4994.4 1099.42
  4994.6 1098.92  4998.4 1099.42  5007.9 1099.42  5030.9 1101.93  5061.1 1101.79
  5081.1 1102.68  5161.5 1102.02  5211.7 1102.66  5230.1 1104.12  5251.8 1103.63
  5312.1 1106.04  5432.6  1108.5  5457.3 1108.22  5492.8 1109.82  5512.9 1109.88
#Mann= 3 ,-1 , 0
  4586.3     .05       0  4994.4     .05       0  4998.4     .05       0
Bank Sta=4994.4,4998.4
XS Rating Curve= 0 ,0
Exp/Cntr=0.3,0.1

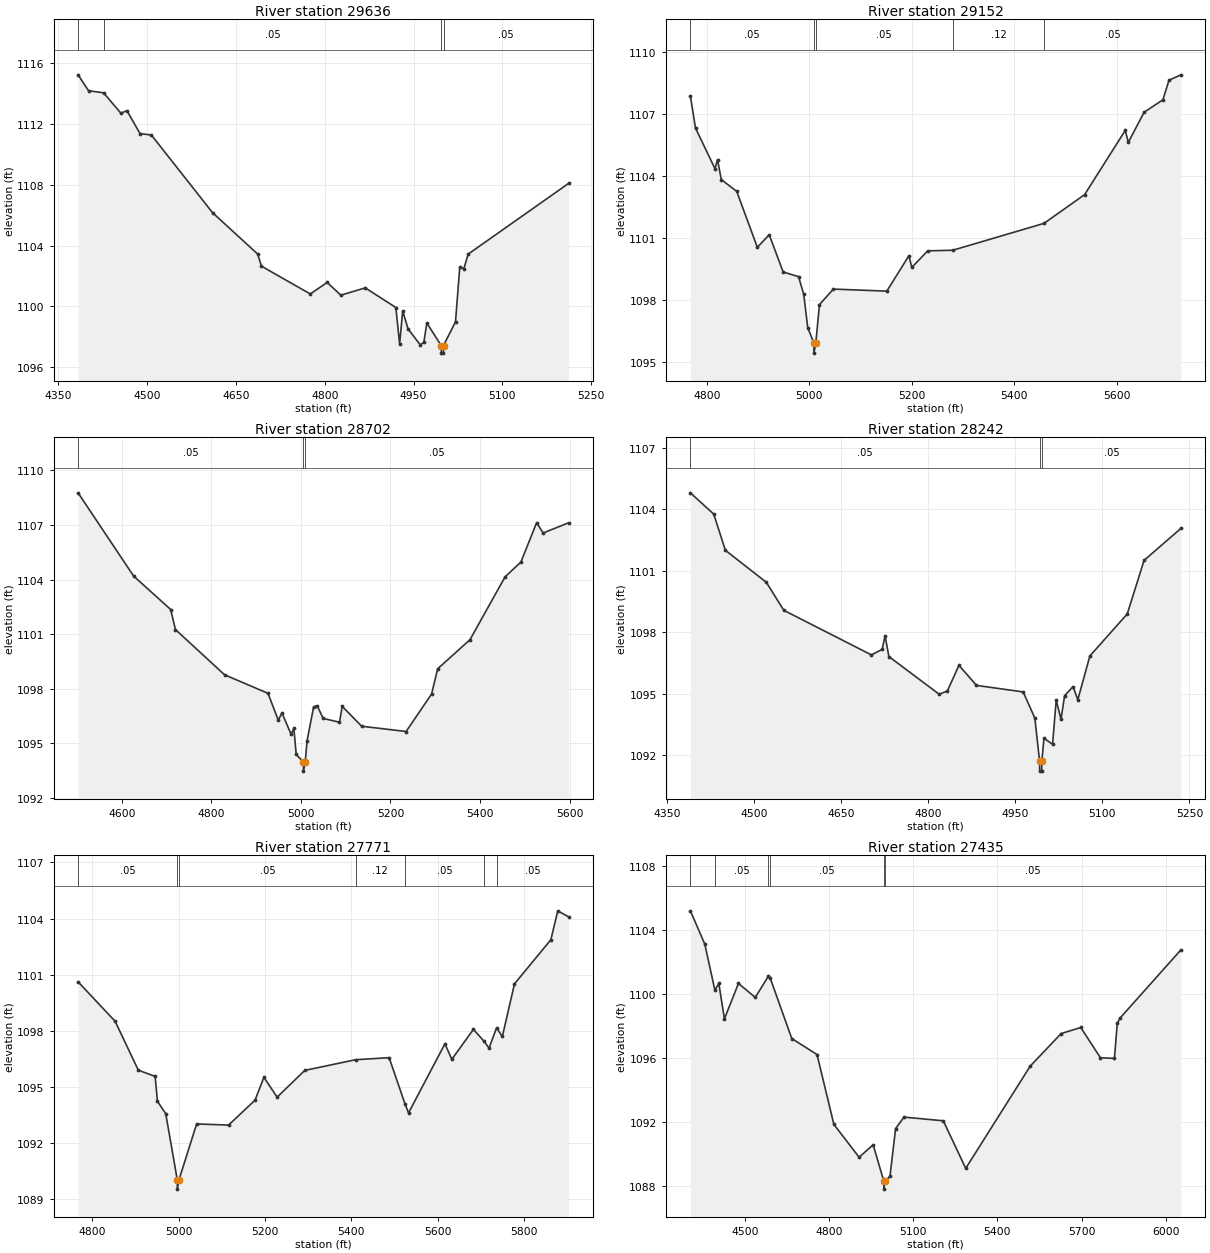
Type RM Length L Ch R = 1 ,29636   ,484,484,484
BEGIN DESCRIPTION:
HARRIS BRANCH 56.0
END DESCRIPTION:
XS GIS Cut Line= 3
       2863255.7     10268353.11      2862658.25       10268506.
      2862505.71     10268653.08
#Sta/Elev= 30
  4383.3 1115.23  4401.1 1114.18  4426.3 1114.05  4455.6 1112.71  4465.9 1112.87
  4487.9 1111.37  4507.2 1111.27  4610.4 1106.17  4686.8 1103.44    4693 1102.65
  4775.6 1100.82  4804.1 1101.58  4827.2 1100.74  4868.5 1101.22  4920.1 1099.93
  4926.5 1097.53  4931.7 1099.71  4940.7 1098.53  4961.4 1097.47  4967.4 1097.64
  4972.5 1098.91  4996.7 1097.43    4997 1096.93  5000.5 1096.93  5000.7 1097.43
  5020.9 1098.99  5028.1 1102.57  5035.1 1102.49  5042.3 1103.44  5211.9 1108.09
#Mann= 4 ,-1 , 0
  4383.3     .12       0  4426.3     .05       0  4996.7     .05       0
  5000.7     .05       0
Bank Sta=4996.7,5000.7
XS Rating Curve= 0 ,0
Exp/Cntr=0.3,0.1

Type RM Length L Ch R = 1 ,29152   ,450,450,450
BEGIN DESCRIPTION:
HARRIS BRANCH 55.0
END DESCRIPTION:
XS GIS Cut Line= 3
      2863005.67     10268053.11        2862775.       10268076.
      2862155.68     10268453.11
#Sta/Elev= 30
  4768.2 1107.87  4778.2 1106.32  4816.1 1104.36  4821.1 1104.79  4828.5 1103.83
  4858.6 1103.26  4898.8 1100.55    4922 1101.16  4949.1 1099.36  4979.2 1099.13
  4989.3 1098.28  4997.1 1096.67  5008.9 1095.93  5009.2 1095.43  5012.9 1095.93
    5020 1097.78  5047.2 1098.53  5151.4 1098.43  5194.4 1100.14  5200.2 1099.58
  5231.1 1100.38  5280.1 1100.41    5458 1101.71  5537.2  1103.1  5616.6 1106.21
  5622.5 1105.63  5653.4 1107.09    5690 1107.69  5701.9 1108.64  5725.1  1108.9
#Mann= 5 ,-1 , 0
  4768.2     .05       0  5008.9     .05       0  5012.9     .05       0
  5280.1     .12       0    5458     .05       0
Bank Sta=5008.9,5012.9
XS Rating Curve= 0 ,0
Exp/Cntr=0.3,0.1

Type RM Length L Ch R = 1 ,28702   ,460,460,460
BEGIN DESCRIPTION:
HARRIS BRANCH 54.0
END DESCRIPTION:
XS GIS Cut Line= 3
      2863005.64     10267603.12       2862524.5       10267732.
       2862055.7      10268103.1
#Sta/Elev= 30
  4501.9 1108.77  4626.1 1104.19  4708.9 1102.35  4719.4 1101.25  4829.2 1098.76
  4926.3 1097.74  4949.3 1096.26  4957.4 1096.66  4978.1 1095.48  4984.1 1095.82
  4989.3 1094.38  5005.4 1093.96  5005.6 1093.46  5009.4 1093.96  5013.7 1095.14
  5028.2 1096.99  5036.2 1097.06  5049.5 1096.36  5085.9 1096.15  5092.3 1097.02
  5135.6 1095.93  5234.9 1095.64  5291.8  1097.7  5305.4 1099.09  5377.6 1100.69
  5456.1 1104.15  5491.4 1104.96  5526.6 1107.13    5541 1106.56  5597.9 1107.12
#Mann= 3 ,-1 , 0
  4501.9     .05       0  5005.4     .05       0  5009.4     .05       0
Bank Sta=5005.4,5009.4
XS Rating Curve= 0 ,0
Exp/Cntr=0.3,0.1

Type RM Length L Ch R = 1 ,28242   ,471,471,471
BEGIN DESCRIPTION:
HARRIS BRANCH 53.0
END DESCRIPTION:
XS GIS Cut Line= 3
      2862855.64     10267603.12       2862249.5       10267667.
      2862105.69     10267853.11
#Sta/Elev= 30
  4390.5 1104.81  4430.7 1103.77  4450.8    1102  4521.2 1100.44  4551.3 1099.07
  4702.2 1096.89  4720.8 1097.16  4725.8 1097.82  4732.3 1096.81  4818.8 1094.97
  4832.9 1095.12    4853 1096.38  4883.2  1095.4  4963.6 1095.08  4983.7  1093.8
  4991.8 1091.71    4992 1091.21  4995.5 1091.21  4995.8 1091.71  4999.4 1092.82
  5014.2 1092.52  5020.5 1094.68  5028.7 1093.74    5035  1094.9  5049.5 1095.34
  5057.7  1094.7  5078.5 1096.84  5142.8 1098.89  5171.8 1101.51  5235.2 1103.07
#Mann= 3 ,-1 , 0
  4390.5     .05       0  4991.8     .05       0  4995.8     .05       0
Bank Sta=4991.8,4995.8
XS Rating Curve= 0 ,0
Exp/Cntr=0.3,0.1

Type RM Length L Ch R = 1 ,27771   ,336,336,336
BEGIN DESCRIPTION:
HARRIS BRANCH 52.0
END DESCRIPTION:
XS GIS Cut Line= 3
      2862705.65      10267403.1        2862489.       10267319.
      2861605.68     10267503.11
#Sta/Elev= 30
  4767.6 1100.62  4853.4 1098.51    4907  1095.9  4945.9 1095.57  4951.2 1094.24
  4970.4 1093.58  4997.1 1090.05  4997.3 1089.55  5001.1 1090.05  5041.9 1093.03
  5115.8 1092.97    5177  1094.3  5197.5 1095.52  5228.1 1094.46  5292.1 1095.89
  5409.7 1096.46  5487.2 1096.57  5523.9  1094.1  5532.1 1093.62  5616.3 1097.31
  5632.2 1096.48  5682.2 1098.08  5706.2 1097.46  5718.4 1097.08  5735.7 1098.16
  5749.1  1097.7  5777.2 1100.51  5861.4 1102.87  5877.3 1104.41  5902.3 1104.09
#Mann= 7 ,-1 , 0
  4767.6     .05       0  4997.1     .05       0  5001.1     .05       0
  5409.7     .12       0  5523.9     .05       0  5706.2     .12       0
  5735.7     .05       0
Bank Sta=4997.1,5001.1
XS Rating Curve= 0 ,0
Exp/Cntr=0.3,0.1

Type RM Length L Ch R = 1 ,27435   ,427,427,427
BEGIN DESCRIPTION:
Mapping XS e1f91281
END DESCRIPTION:
XS GIS Cut Line= 2
      2863106.97     10266997.23      2861358.87     10266997.23
#Sta/Elev= 30
  4306.1 1105.18  4357.4  1103.1  4393.4 1100.22  4407.4 1100.64  4427.4 1098.43
  4477.4 1100.64  4537.4 1099.77  4583.5 1101.08  4590.5 1100.98  4667.4  1097.2
  4757.4  1096.2  4817.4 1091.84  4907.4 1089.78  4957.4 1090.56  4995.4 1088.29
  4995.6 1087.79  4999.4 1088.29  5017.4 1088.59  5037.4 1091.57  5067.4 1092.29
  5207.4 1092.06  5287.4 1089.09  5517.4 1095.48  5627.4 1097.51  5697.4 1097.89
  5767.4    1096  5817.4 1095.96  5827.4 1098.15  5837.4 1098.48  6054.2 1102.74
#Mann= 6 ,-1 , 0
  4306.1     .12       0  4393.4     .05       0  4583.5     .12       0
  4590.5     .05       0  4995.4     .05       0  4999.4     .05       0
Bank Sta=4995.4,4999.4
XS Rating Curve= 0 ,0
Exp/Cntr=0.3,0.1

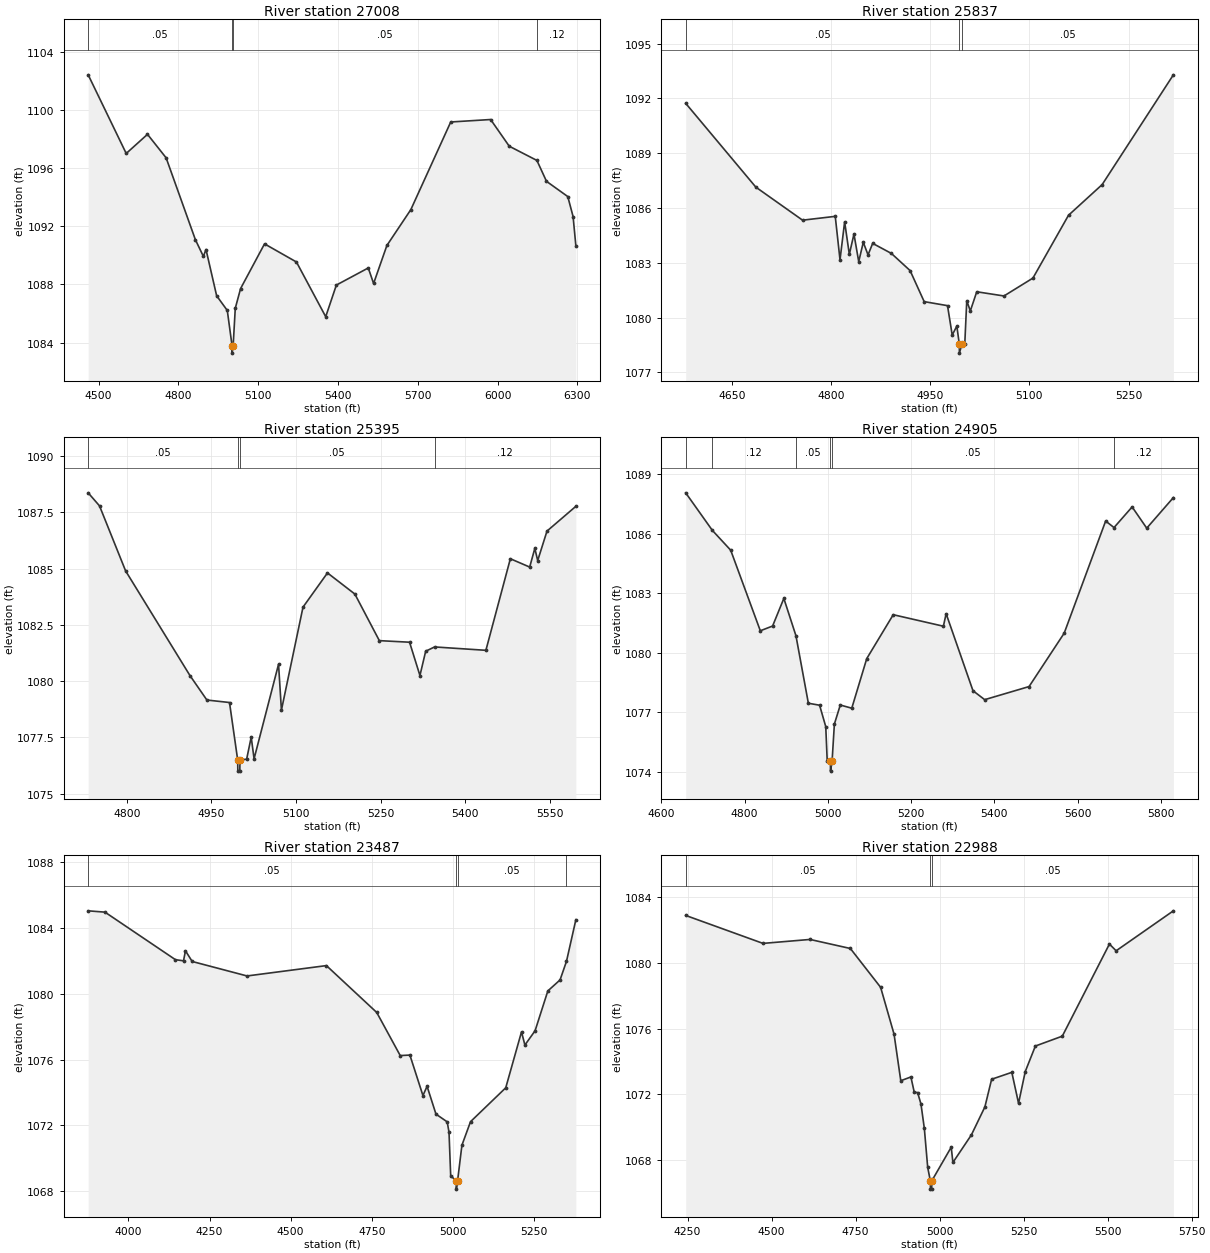
Type RM Length L Ch R = 1 ,27008   ,1171,1171,1171
BEGIN DESCRIPTION:
Mapping XS da566b07
END DESCRIPTION:
XS GIS Cut Line= 2
      2862898.67     10266643.06      2861065.27     10266643.06
#Sta/Elev= 30
  4460.6 1102.45  4603.6 1097.03  4683.6 1098.35  4753.6 1096.73  4863.6 1091.09
  4893.6 1089.94  4903.6 1090.41  4943.6 1087.22  4983.6 1086.21  5001.6 1083.77
  5001.8 1083.27  5005.6 1083.77  5013.6 1086.36  5033.6 1087.72  5123.6  1090.8
  5243.6 1089.55  5353.6 1085.78  5393.6 1087.96  5513.6 1089.14  5533.6 1088.07
  5583.6 1090.69  5673.6 1093.16  5823.6  1099.2  5973.6 1099.37  6043.6 1097.53
  6147.6 1096.55  6183.6 1095.11  6263.6 1094.06  6283.6 1092.68    6294 1090.67
#Mann= 4 ,-1 , 0
  4460.6     .05       0  5001.6     .05       0  5005.6     .05       0
  6147.6     .12       0
Bank Sta=5001.6,5005.6
XS Rating Curve= 0 ,0
Exp/Cntr=0.3,0.1

Type RM Length L Ch R = 1 ,25837   ,442,442,442
BEGIN DESCRIPTION:
HARRIS BRANCH 48.0
END DESCRIPTION:
XS GIS Cut Line= 3
      2862055.66     10265753.14      2861762.75       10266054.
      2861655.68     10266353.12
#Sta/Elev= 30
  4580.1 1091.73  4686.2 1087.14  4756.9 1085.33  4806.3 1085.54  4813.5 1083.16
  4820.5 1085.24  4827.6 1083.46  4834.6 1084.57  4841.8 1083.06  4848.7 1084.12
  4855.9 1083.43  4862.9 1084.06  4891.2 1083.51  4919.5 1082.57  4940.8 1080.87
  4976.1 1080.65  4983.2 1079.04  4990.2 1079.53  4993.9 1078.55  4994.1 1078.05
  4997.9 1078.55  5002.2 1078.55  5005.2 1080.92  5010.6 1080.36  5020.3 1081.41
  5061.5 1081.18  5105.3 1082.16  5159.1  1085.6    5210 1087.28  5317.7 1093.29
#Mann= 3 ,-1 , 0
  4580.1     .05       0  4993.9     .05       0  4997.9     .05       0
Bank Sta=4993.9,4997.9
XS Rating Curve= 0 ,0
Exp/Cntr=0.3,0.1

Type RM Length L Ch R = 1 ,25395   ,490,490,490
BEGIN DESCRIPTION:
HARRIS BRANCH 47.0
END DESCRIPTION:
XS GIS Cut Line= 3
      2861955.71     10265753.11      2861687.75       10265773.
      2861105.71      10265903.1
#Sta/Elev= 30
  4731.3 1088.37  4751.4 1087.79  4797.7  1084.9  4911.8 1080.25  4941.9 1079.16
    4982 1079.05  4996.5  1076.5  4996.8    1076  5000.3    1076  5000.5  1076.5
  5012.4 1076.53  5020.5 1077.51  5025.6 1076.55    5069 1080.75  5074.1 1078.71
  5112.4 1083.29  5155.8 1084.81  5204.4 1083.87  5247.8  1081.8  5301.4 1081.73
  5319.8 1080.25    5330 1081.33  5345.8 1081.52  5436.8 1081.37  5480.2 1085.44
  5514.5 1085.07  5523.6  1085.9  5528.7 1085.36  5545.2 1086.67  5596.4 1087.77
#Mann= 4 ,-1 , 0
  4731.3     .05       0  4996.5     .05       0  5000.5     .05       0
  5345.8     .12       0
Bank Sta=4996.5,5000.5
XS Rating Curve= 0 ,0
Exp/Cntr=0.3,0.1

Type RM Length L Ch R = 1 ,24905   ,1418,1418,1418
BEGIN DESCRIPTION:
HARRIS BRANCH 46.0
END DESCRIPTION:
XS GIS Cut Line= 3
      2862005.69     10265503.12      2861728.25       10265304.
       2861105.7     10265853.09
#Sta/Elev= 30
  4658.5 1088.06  4722.5 1086.17  4766.6 1085.17  4837.8 1081.11  4867.3 1081.35
  4894.3 1082.74  4923.4 1080.86  4953.2 1077.46  4980.2 1077.36    4995 1076.28
  4998.5 1074.55  5006.2 1074.54  5006.4 1074.04  5010.2 1074.54  5015.7 1076.41
  5029.9 1077.37  5057.5 1077.21  5093.5 1079.71  5157.1 1081.92  5277.6 1081.34
  5284.2 1081.97  5348.7 1078.09  5376.8 1077.64  5483.4  1078.3  5567.8 1080.99
  5667.4 1086.64  5687.5 1086.31    5731 1087.35  5766.1 1086.28  5830.1 1087.82
#Mann= 6 ,-1 , 0
  4658.5     .05       0  4722.5     .12       0  4923.4     .05       0
  5006.2     .05       0  5010.2     .05       0  5687.5     .12       0
Bank Sta=5006.2,5010.2
XS Rating Curve= 0 ,0
Exp/Cntr=0.3,0.1

Type RM Length L Ch R = 1 ,23487   ,499,499,499
BEGIN DESCRIPTION:
HARRIS BRANCH 45.0
END DESCRIPTION:
XS GIS Cut Line= 3
      2861905.71      10264753.1        2860819.       10265041.
      2860705.69     10265403.09
#Sta/Elev= 30
  3875.8 1085.05  3927.6 1084.97  4144.8 1082.08  4169.7 1082.01  4175.8 1082.62
  4196.5 1081.97  4365.6 1081.09  4610.3 1081.72  4765.5 1078.87  4837.9 1076.25
  4867.7 1076.28  4907.9 1073.82  4920.7 1074.38  4948.1 1072.69  4982.7 1072.22
  4988.3 1071.59  4993.5 1068.94  5010.7 1068.63  5010.9 1068.13  5014.7 1068.63
  5028.1  1070.8  5054.6 1072.23  5163.2 1074.29  5211.8 1077.69  5222.3 1076.89
  5253.7 1077.76    5293 1080.18  5330.7 1080.85  5350.5 1081.98  5379.4 1084.51
#Mann= 4 ,-1 , 0
  3875.8     .05       0  5010.7     .03       0  5014.7     .05       0
  5350.5     .12       0
Bank Sta=5010.7,5014.7
XS Rating Curve= 0 ,0
Exp/Cntr=0.3,0.1

Type RM Length L Ch R = 1 ,22988   ,497,497,497
BEGIN DESCRIPTION:
HARRIS BRANCH 44.0
END DESCRIPTION:
XS GIS Cut Line= 3
      2861705.64     10264753.11      2860950.25       10264766.
      2860255.64     10264803.11
#Sta/Elev= 30
  4244.5 1082.88  4474.5 1081.18  4614.5 1081.42  4734.5 1080.87  4824.5 1078.51
  4864.5 1075.66  4884.5 1072.83  4914.6 1073.06  4924.6 1072.13  4934.6 1072.11
  4944.6 1071.41  4954.6 1069.93  4964.6 1067.56  4972.5 1066.74  4972.8 1066.24
  4976.4 1066.24  4976.7 1066.74  5034.6 1068.79  5039.6 1067.86  5094.7 1069.54
  5134.8 1071.24  5154.8 1072.92  5214.9 1073.34  5234.9 1071.46  5254.9 1073.39
    5285 1074.94  5365.1 1075.54  5505.3 1081.14  5525.3 1080.73  5695.6 1083.16
#Mann= 3 ,-1 , 0
  4244.5     .05       0  4972.5     .03       0  4976.7     .05       0
Bank Sta=4972.5,4976.7
XS Rating Curve= 0 ,0
Exp/Cntr=0.3,0.1