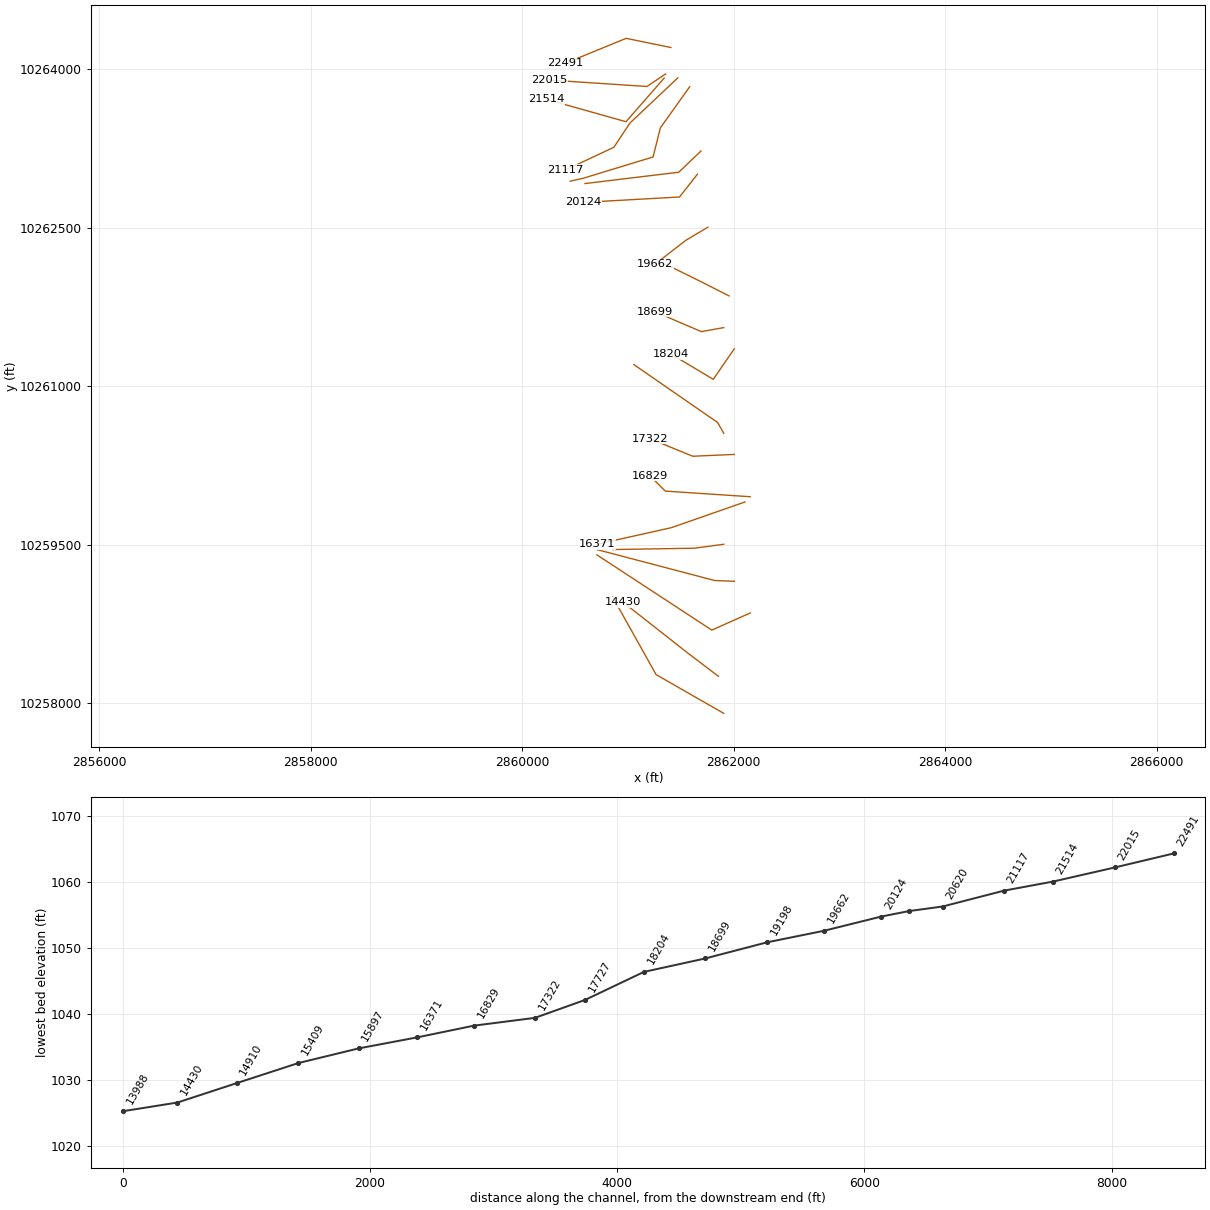
HEC-RAS study HARRIS BRANCH.prj: HARRIS BRANCH Base Level Engineering

--- HARRIS BRANCH.g01 (geometry) --- (continued)

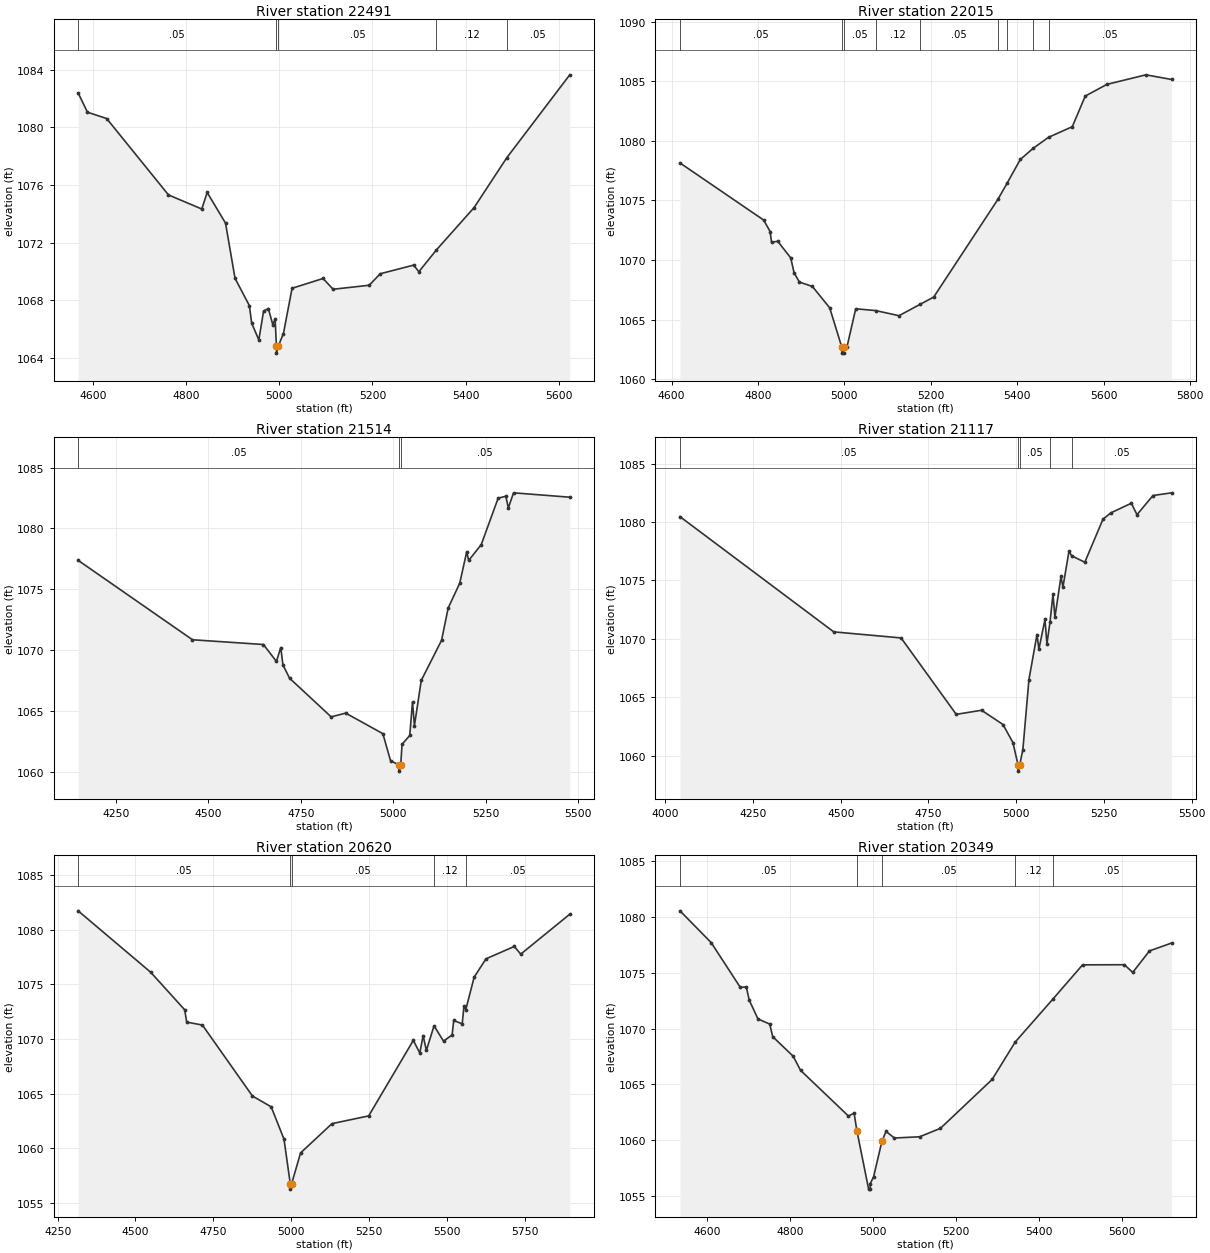
Type RM Length L Ch R = 1 ,22491   ,476,476,476
BEGIN DESCRIPTION:
HARRIS BRANCH 43.0
END DESCRIPTION:
XS GIS Cut Line= 3
      2861405.72     10264203.11      2860982.75       10264290.
      2860405.68     10264053.11
#Sta/Elev= 30
  4568.2  1082.4  4588.3 1081.06  4629.5 1080.62  4762.2 1075.31  4833.7 1074.33
  4845.3 1075.48  4884.7 1073.35  4905.1 1069.51  4935.8 1067.62  4940.9 1066.39
  4956.2 1065.23  4966.4 1067.23  4976.6 1067.41  4986.2 1066.29  4991.3 1066.69
  4993.9 1064.81  4994.1 1064.31  4998.1 1064.81    5009 1065.67  5027.6 1068.82
  5094.1  1069.5  5115.7 1068.75  5193.1 1069.03    5217 1069.83  5288.7 1070.43
  5299.8 1069.97  5337.6 1071.49  5418.4 1074.43  5488.7  1077.9  5623.8 1083.66
#Mann= 5 ,-1 , 0
  4568.2     .05       0  4993.9     .05       0  4998.1     .05       0
  5337.6     .12       0  5488.7     .05       0
Bank Sta=4993.9,4998.1
XS Rating Curve= 0 ,0
Exp/Cntr=0.3,0.1

Type RM Length L Ch R = 1 ,22015   ,501,501,501
BEGIN DESCRIPTION:
HARRIS BRANCH 42.0
END DESCRIPTION:
XS GIS Cut Line= 3
      2861355.72     10263953.13      2861179.14     10263834.56
      2860256.33     10263895.33
#Sta/Elev= 30
  4619.5 1078.14  4813.1 1073.35  4828.1 1072.39  4831.3 1071.49  4845.7 1071.57
  4875.7 1070.18  4883.5 1068.93  4895.8 1068.15  4925.9 1067.78  4965.9 1065.99
  4993.9 1062.69  4994.2 1062.19  4997.9 1062.19  4998.2 1062.69    5006 1062.73
  5026.1 1065.91  5072.1 1065.76  5126.3 1065.33  5174.4 1066.27  5206.5 1066.89
    5355 1075.08  5376.3 1076.44  5406.9 1078.43  5437.1 1079.38  5472.2 1080.29
  5527.2 1081.18  5557.2 1083.75  5607.3 1084.73  5697.5 1085.53    5757 1085.14
#Mann= 9 ,-1 , 0
  4619.5     .05       0  4993.9     .05       0  4998.2     .05       0
  5072.1     .12       0  5174.4     .05       0    5355     .12       0
  5376.3     .05       0  5437.1     .12       0  5472.2     .05       0
Bank Sta=4993.9,4998.2
XS Rating Curve= 0 ,0
Exp/Cntr=0.3,0.1

Type RM Length L Ch R = 1 ,21514   ,397,397,397
BEGIN DESCRIPTION:
HARRIS BRANCH 41.0
END DESCRIPTION:
XS GIS Cut Line= 3
      2861341.64     10263913.68      2860981.29     10263501.04
      2860229.34     10263712.66
#Sta/Elev= 30
  4147.9 1077.38    4457 1070.85  4648.8 1070.46  4683.9 1069.07  4695.7 1070.21
  4701.6 1068.78  4719.5 1067.69    4832 1064.51  4871.2 1064.82  4971.7 1063.13
  4992.4 1060.91  5015.6 1060.55  5015.9 1060.05  5019.9 1060.55  5023.6 1062.26
  5044.4 1062.98  5051.8 1065.75    5057 1063.79  5075.5 1067.51  5130.3  1070.8
  5148.3 1073.47  5179.4 1075.49  5198.4 1078.09  5203.6 1077.37  5237.6 1078.67
  5283.3 1082.49  5304.1 1082.65  5310.9 1081.69  5324.9 1082.93  5476.9 1082.57
#Mann= 3 ,-1 , 0
  4147.9     .05       0  5015.6     .03       0  5019.9     .05       0
Bank Sta=5015.6,5019.9
XS Rating Curve= 0 ,0
Exp/Cntr=0.3,0.1

Type RM Length L Ch R = 1 ,21117   ,497,497,497
BEGIN DESCRIPTION:
Mapping XS 8f1dad28
END DESCRIPTION:
XS GIS Cut Line= 4
      2861471.66     10263916.51      2861018.04     10263488.32
      2860866.82     10263259.39      2860411.74     10263045.98
#Sta/Elev= 30
  4042.1 1080.45  4480.2 1070.59  4672.1 1070.07  4829.2 1063.53  4901.4 1063.88
  4962.5 1062.66  4990.8 1061.11  5005.6 1059.17  5005.9 1058.67  5009.9 1059.17
  5019.1 1060.52  5036.4 1066.51  5059.3 1070.36  5064.8 1069.11  5082.1 1071.65
  5087.6 1069.56  5096.5 1071.45  5104.9 1073.82  5110.4 1071.84  5127.7 1075.34
  5133.2 1074.41  5150.5  1077.5  5157.9  1077.1  5195.6 1076.55  5247.4 1080.24
  5270.2 1080.78  5328.1  1081.6  5344.2 1080.62  5389.8 1082.26  5442.9 1082.49
#Mann= 5 ,-1 , 0
  4042.1     .05       0  5005.6     .03       0  5009.9     .05       0
  5096.5     .12       0  5157.9     .05       0
Bank Sta=5005.6,5009.9
XS Rating Curve= 0 ,0
Exp/Cntr=0.3,0.1

Type RM Length L Ch R = 1 ,20620   ,271,271,271
BEGIN DESCRIPTION:
Mapping XS 76d6d373
END DESCRIPTION:
XS GIS Cut Line= 5
       2861583.3      10263831.7      2861306.33      10263443.1
      2861237.08     10263167.53      2860574.29     10262965.44
      2860452.78     10262938.59
#Sta/Elev= 30
  4315.8 1081.73  4548.9 1076.11  4657.9 1072.68  4664.5 1071.55  4714.9 1071.28
  4875.5 1064.79  4935.7  1063.8  4976.9 1060.84    4997 1056.77  4997.3 1056.27
  5001.4 1056.77  5030.1 1059.58  5130.9 1062.26  5248.8 1062.97  5392.2 1069.88
    5413 1068.72  5423.6 1070.31  5434.1 1068.96  5458.7 1071.21  5489.1 1069.81
  5516.7 1070.37  5521.9  1071.7  5549.1 1071.39  5554.7 1072.98  5560.7  1072.7
  5587.6 1075.67  5625.6 1077.34  5716.3 1078.47  5737.2 1077.77  5894.5 1081.42
#Mann= 5 ,-1 , 0
  4315.8     .05       0    4997     .05       0  5001.4     .05       0
  5458.7     .12       0  5560.7     .05       0
Bank Sta=4997,5001.4
XS Rating Curve= 0 ,0
Exp/Cntr=0.3,0.1

Type RM Length L Ch R = 1 ,20349   ,225,225,225
BEGIN DESCRIPTION:
HARRIS BRANCH 40.0
END DESCRIPTION:
XS GIS Cut Line= 3
      2861690.69     10263224.03      2861480.15     10263023.38
      2860592.67     10262915.98
#Sta/Elev= 30
  4534.4 1080.57  4609.5 1077.72  4679.9 1073.69  4694.1 1073.75  4701.3 1072.55
  4722.4 1070.86  4750.7  1070.4  4757.9 1069.27  4807.3 1067.51  4824.9 1066.25
  4940.5 1062.14    4954 1062.41  4960.7 1060.83    4989 1055.58  4992.8 1055.58
  4993.1 1056.08    5001 1056.69  5021.1 1059.88  5030.9 1060.76  5051.3 1060.17
  5111.8 1060.28  5162.1 1061.04  5286.7 1065.43  5342.3 1068.79  5433.2 1072.65
  5504.6 1075.72  5605.4 1075.73  5625.5 1075.04  5665.8 1076.97  5719.2 1077.68
#Mann= 5 ,-1 , 0
  4534.4     .05       0  4960.7     .05       0  5021.1     .05       0
  5342.3     .12       0  5433.2     .05       0
Bank Sta=4960.7,5021.1
XS Rating Curve= 0 ,0
Exp/Cntr=0.3,0.1

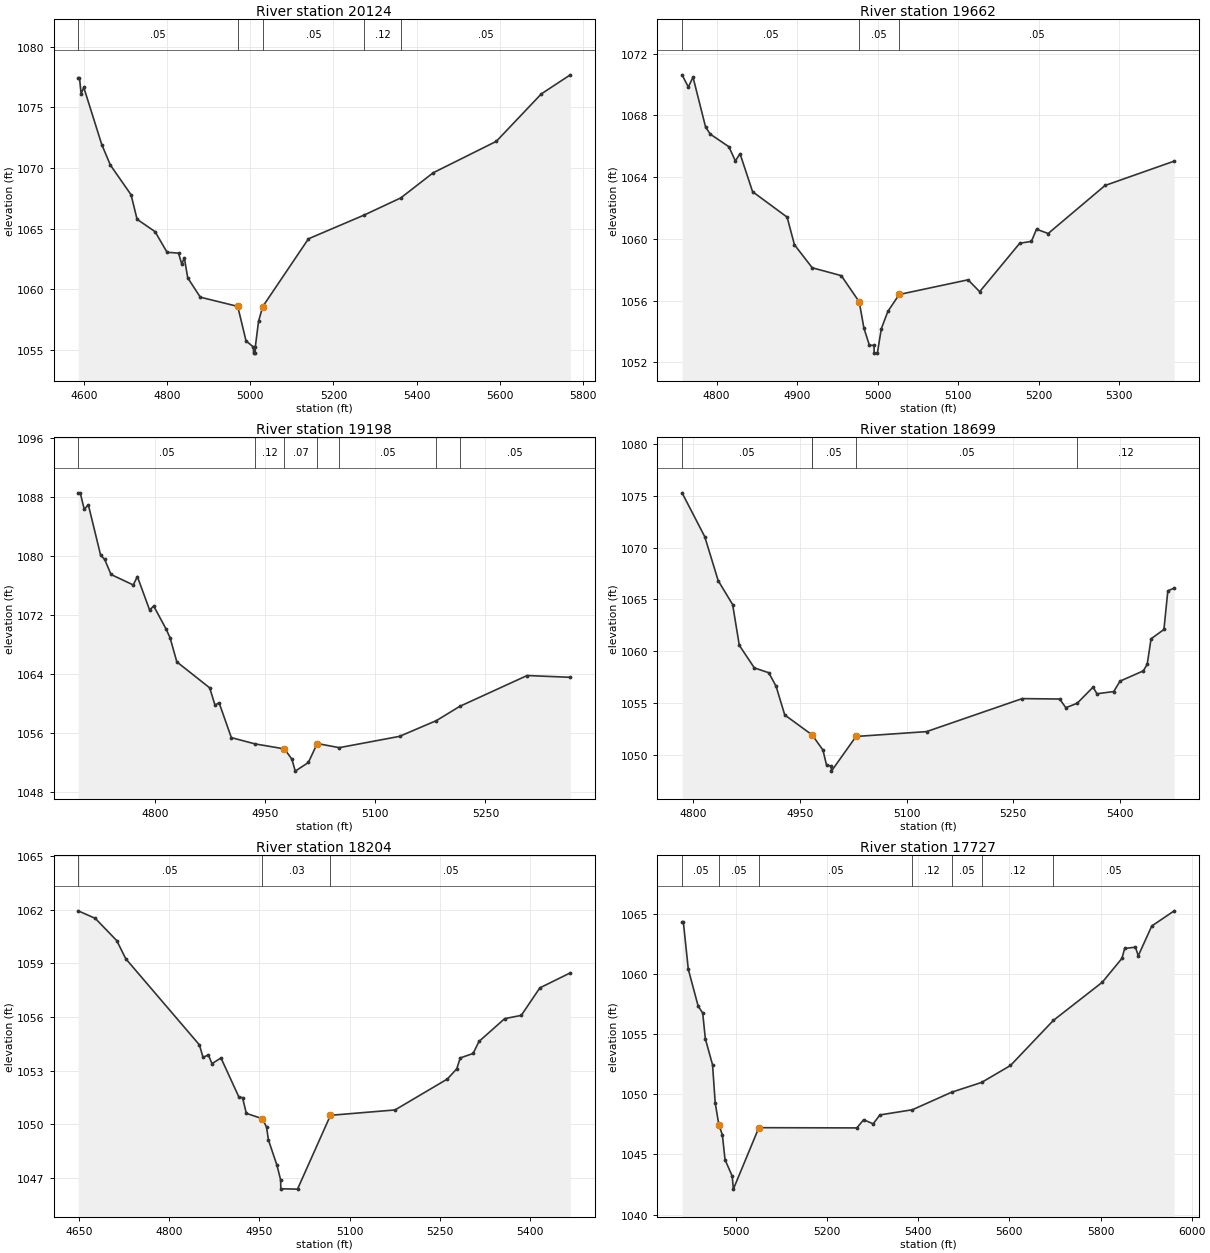
Type RM Length L Ch R = 1 ,20124   ,462,462,462
BEGIN DESCRIPTION:
HARRIS BRANCH 39.0
END DESCRIPTION:
XS GIS Cut Line= 3
      2861655.67      10263003.1      2861487.22     10262788.79
      2860576.02     10262738.01
#Sta/Elev= 30
  4585.2 1077.43  4588.4 1077.43  4592.4 1076.13  4598.8 1076.64  4642.1 1071.93
  4662.9 1070.24  4712.6  1067.8  4727.1 1065.78  4770.4 1064.76  4799.3 1063.06
  4826.9 1062.99  4834.6  1062.1    4841 1062.59  4849.1 1060.95  4879.4 1059.36
  4969.5  1058.6  4989.5 1055.76  5007.3 1055.25  5007.6 1054.75  5011.5 1054.75
  5011.8 1055.25  5019.6 1057.37  5029.6 1058.58  5139.8 1064.17  5273.5 1066.12
  5362.2 1067.54  5440.2 1069.61  5592.2  1072.2  5700.6 1076.11  5770.4 1077.68
#Mann= 5 ,-1 , 0
  4585.2     .05       0  4969.5     .05       0  5029.6     .05       0
  5273.5     .12       0  5362.2     .05       0
Bank Sta=4969.5,5029.6
XS Rating Curve= 0 ,0
Exp/Cntr=0.3,0.1

Type RM Length L Ch R = 1 ,19662   ,464,464,464
BEGIN DESCRIPTION:
HARRIS BRANCH 38.0
END DESCRIPTION:
XS GIS Cut Line= 3
      2861755.68     10262503.11        2861547.       10262379.
      2861255.71     10262153.13
#Sta/Elev= 30
  4757.2 1070.63    4765 1069.84  4770.8 1070.48  4786.4 1067.25  4792.2 1066.79
  4815.4 1065.97  4823.4 1065.05  4829.2 1065.52  4844.8 1063.06  4887.7 1061.41
  4896.8 1059.62  4918.9 1058.13    4955 1057.62  4977.3 1055.92  4983.1 1054.22
  4989.9 1053.11  4995.6  1053.1  4995.9  1052.6  4999.8  1052.6  5004.7 1054.18
  5012.9 1055.31    5027  1056.4  5112.5 1057.35  5126.9 1056.58  5176.7 1059.72
  5191.2 1059.84  5197.5 1060.63    5212 1060.35  5282.6 1063.46  5368.6 1065.04
#Mann= 3 , 0 , 0
  4757.2     .05       0  4977.3     .05       0    5027     .05       0
Bank Sta=4977.3,5027
XS Rating Curve= 0 ,0
Exp/Cntr=0.3,0.1

Type RM Length L Ch R = 1 ,19198   ,499,499,499
BEGIN DESCRIPTION:
HARRIS BRANCH 37.0
END DESCRIPTION:
XS GIS Cut Line= 3
      2861955.67     10261853.12       2861683.5       10261991.
      2861355.69     10262153.11
#Sta/Elev= 30
  4694.9 1088.54  4697.7 1088.54  4703.2 1086.32  4708.8 1086.92  4725.5  1080.1
  4731.1 1079.51  4739.7 1077.48    4770 1076.06  4775.6  1077.2  4792.3 1072.67
  4797.9  1073.2  4814.6 1070.12  4820.2  1068.9  4829.4 1065.64  4874.2 1062.12
  4881.4 1059.78    4887  1060.1  4903.7 1055.38  4935.9 1054.53  4976.1 1053.85
  4986.3 1052.44  4990.8 1050.84  5008.7 1052.01  5020.7 1054.58  5050.8 1054.02
  5132.9 1055.55  5183.3 1057.69  5215.1 1059.62  5306.8 1063.79  5365.7 1063.55
#Mann= 7 ,-1 , 0
  4694.9     .05       0  4935.9     .12       0  4976.1     .07       0
  5020.7     .12       0  5050.8     .05       0  5183.3     .12       0
  5215.1     .05       0
Bank Sta=4976.1,5020.7
XS Rating Curve= 0 ,0
Exp/Cntr=0.3,0.1

Type RM Length L Ch R = 1 ,18699   ,495,495,495
BEGIN DESCRIPTION:
HARRIS BRANCH 36.0
END DESCRIPTION:
XS GIS Cut Line= 3
       2861905.7     10261553.12       2861693.5       10261515.
       2861255.7      10261703.1
#Sta/Elev= 30
  4784.4  1075.3  4816.3 1071.06  4835.2 1066.81  4855.5  1064.5  4864.9 1060.56
    4886 1058.38  4906.3 1057.91  4916.5 1056.62  4928.8 1053.83  4967.3  1051.9
  4982.5 1050.44  4987.6 1048.97  4994.1  1048.9  4994.4  1048.4    5029 1051.75
  5128.2 1052.22  5262.7 1055.41  5315.3 1055.37  5324.1 1054.53    5340 1054.96
  5362.4 1056.52  5367.8 1055.88  5391.4 1056.09  5400.3  1057.1    5433 1058.09
  5438.5 1058.73  5443.9 1061.19    5462 1062.09  5467.5 1065.83  5476.5 1066.09
#Mann= 5 ,-1 , 0
  4784.4     .05       0  4967.3     .12       0  4967.3     .05       0
    5029     .05       0    5340     .12       0
Bank Sta=4967.3,5029
XS Rating Curve= 0 ,0
Exp/Cntr=0.3,0.1

Type RM Length L Ch R = 1 ,18204   ,477,477,477
BEGIN DESCRIPTION:
HARRIS BRANCH 35.0
END DESCRIPTION:
XS GIS Cut Line= 3
      2862005.67     10261353.09      2861806.25       10261064.
      2861405.69     10261303.11
#Sta/Elev= 30
  4648.8 1061.94  4677.2 1061.52    4713 1060.27  4727.9 1059.26  4850.3 1054.44
  4856.3 1053.74  4865.1 1053.88  4871.2 1053.39  4886.1 1053.71  4915.9 1051.52
  4921.9 1051.49  4928.2 1050.61 4954.92 1050.31 4961.77 1049.84 4964.97 1049.12
 4979.15  1047.7  4985.2 1046.89  4985.5 1046.39 5013.27 1046.37 5067.99  1050.5
 5175.25  1050.8  5262.2 1052.53  5277.8  1053.1  5283.6 1053.71    5305 1053.96
  5314.7 1054.63  5357.5 1055.91    5385 1056.09  5415.9 1057.63  5466.5 1058.47
#Mann= 3 , 0 , 0
  4648.8     .05       0 4954.92     .03       0 5067.99     .05       0
Bank Sta=4954.92,5067.99
XS Rating Curve= 0 ,0
Exp/Cntr=0.3,0.1

Type RM Length L Ch R = 1 ,17727   ,405,405,405
BEGIN DESCRIPTION:
HARRIS BRANCH 34.0
END DESCRIPTION:
XS GIS Cut Line= 3
       2861905.7     10260553.09      2861846.75       10260656.
      2861055.71     10261203.09
#Sta/Elev= 30
  4881.4 1064.29  4884.3 1064.29  4895.1  1060.4  4916.7 1057.34  4926.7 1056.76
  4932.5 1054.62  4948.3 1052.46  4954.1 1049.31  4962.1 1047.48  4969.9 1046.62
  4975.7 1044.57  4991.5  1043.2    4994 1042.12  5049.9 1047.23  5265.1 1047.21
  5279.9 1047.89  5300.9 1047.55  5315.7 1048.29    5387 1048.72  5473.2 1050.18
  5538.8 1050.99  5602.3  1052.4  5696.5 1056.15  5803.8 1059.32  5846.9  1061.3
    5853 1062.13  5876.7 1062.24  5882.8 1061.52  5912.5    1064  5961.8 1065.26
#Mann= 7 ,-1 , 0
  4881.4     .05       0  4962.1     .05       0  5049.9     .05       0
    5387     .12       0  5473.2     .05       0  5538.8     .12       0
  5696.5     .05       0
Bank Sta=4962.1,5049.9
XS Rating Curve= 0 ,0
Exp/Cntr=0.3,0.1

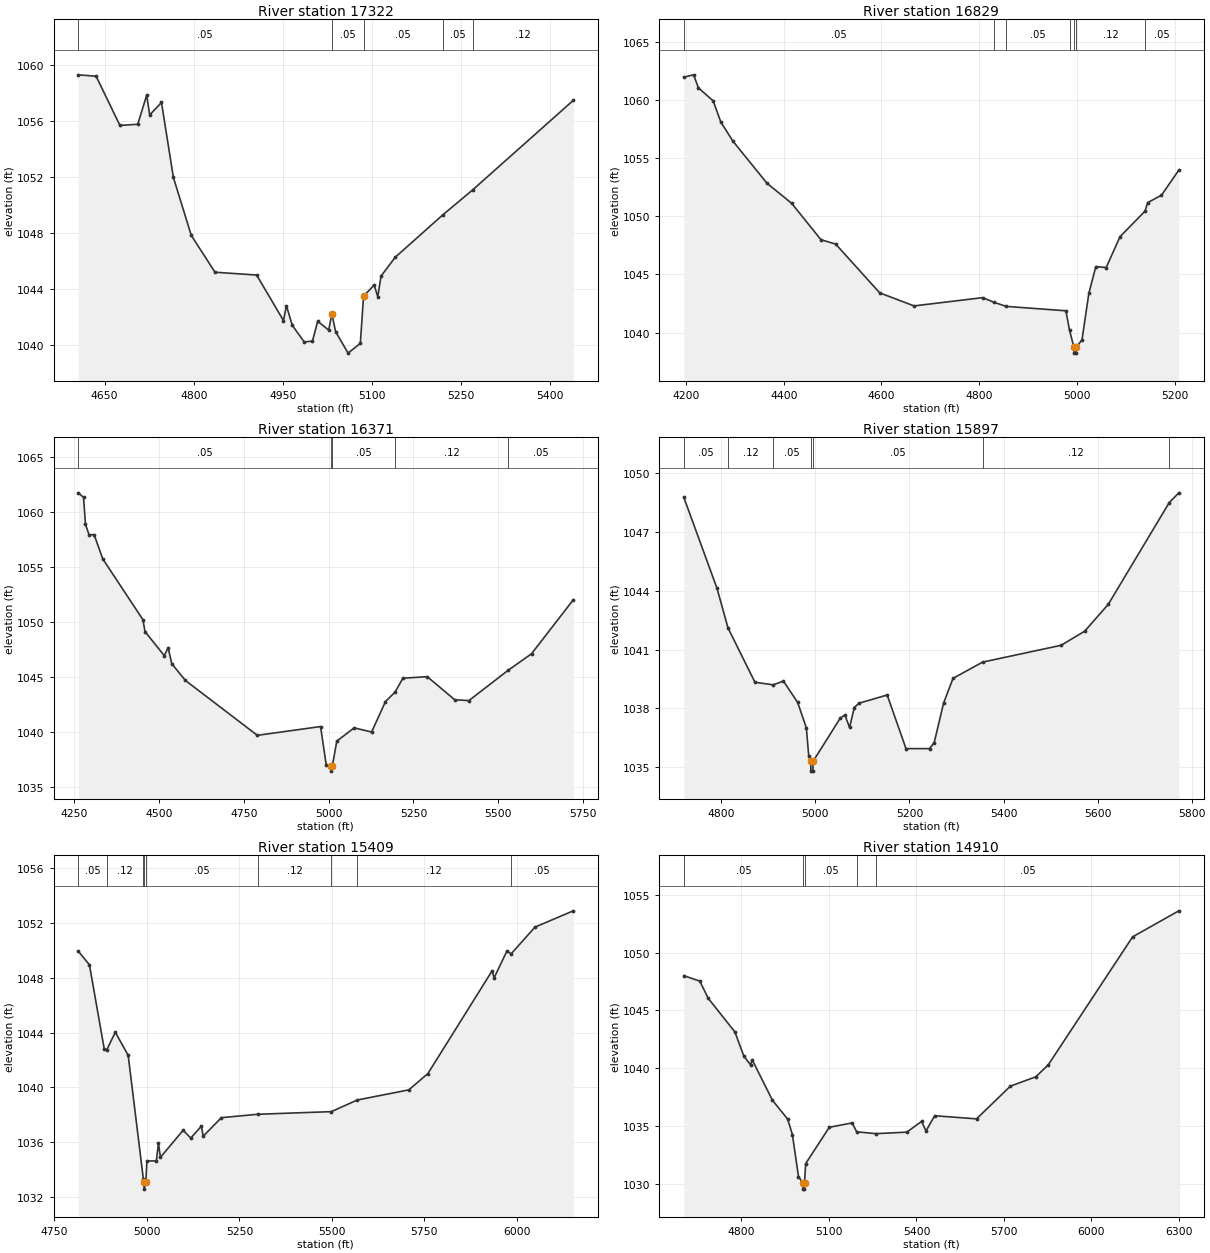
Type RM Length L Ch R = 1 ,17322   ,493,493,493
BEGIN DESCRIPTION:
HARRIS BRANCH 33.0
END DESCRIPTION:
XS GIS Cut Line= 3
      2862005.68     10260353.11      2861611.75       10260336.
      2861205.69     10260503.11
#Sta/Elev= 30
  4605.7 1059.33  4635.7 1059.23  4675.8 1055.71  4705.8 1055.79  4720.9 1057.88
  4725.9 1056.46  4745.8 1057.35  4765.8 1051.99  4795.9 1047.84  4835.9  1045.2
    4906    1045  4951.2 1041.74  4956.2  1042.8    4966  1041.4  4986.1 1040.21
    5000 1040.27  5008.8 1041.69  5027.3 1041.06  5032.7 1042.22    5039 1040.94
    5060 1039.41  5080.6 1040.11    5086 1043.49  5103.9 1044.28    5110 1043.45
  5115.4 1044.92  5139.3 1046.27    5219 1049.29  5269.6 1051.09  5439.1  1057.5
#Mann= 5 ,-1 , 0
  4605.7     .05       0  5032.7     .05       0    5086     .05       0
    5219     .05       0  5269.6     .12       0
Bank Sta=5032.7,5086
XS Rating Curve= 0 ,0
Exp/Cntr=0.3,0.1

Type RM Length L Ch R = 1 ,16829   ,458,458,458
BEGIN DESCRIPTION:
HARRIS BRANCH 32.0
END DESCRIPTION:
XS GIS Cut Line= 3
      2862155.66     10259953.11        2861353.       10260006.
      2861205.68     10260153.12
#Sta/Elev= 30
  4195.6 1061.96  4215.6 1062.16  4225.6 1061.03  4255.7 1059.92  4271.2 1058.11
  4295.8 1056.47  4365.9 1052.83  4416.1 1051.12  4476.2 1047.98  4506.2 1047.61
  4596.4 1043.41  4666.6 1042.29  4806.9    1043  4830.1  1042.6  4855.2 1042.25
  4977.3 1041.87  4984.8 1040.18  4993.7 1038.73    4994 1038.23  4998.2 1038.23
  4998.6 1038.73  5010.2 1039.38  5024.3 1043.39  5038.5 1045.67  5059.7 1045.59
    5088 1048.24  5139.1 1050.44  5144.6 1051.17  5172.8 1051.81  5208.2 1053.96
#Mann= 7 ,-1 , 0
  4195.6     .05       0  4830.1     .12       0  4855.2     .05       0
  4984.8     .12       0  4993.7     .07       0  4998.6     .12       0
  5139.1     .05       0
Bank Sta=4993.7,4998.6
XS Rating Curve= 0 ,0
Exp/Cntr=0.3,0.1

Type RM Length L Ch R = 1 ,16371   ,474,474,474
BEGIN DESCRIPTION:
HARRIS BRANCH 31.0
END DESCRIPTION:
XS GIS Cut Line= 3
      2862105.67     10259903.11       2861409.5       10259660.
      2860705.67     10259503.11
#Sta/Elev= 30
  4262.6 1061.74  4278.1 1061.33  4283.8 1058.87  4294.4 1057.93  4309.2 1057.94
  4334.9 1055.73  4453.2 1050.21  4459.1 1049.14    4516 1046.95  4527.4 1047.67
    4538 1046.22  4578.1  1044.7  4790.2 1039.71  4976.5 1040.51  4993.4 1036.99
  5006.4 1036.96  5006.8 1036.46  5011.3 1036.96  5024.4 1039.19  5075.6 1040.39
  5126.9 1040.01  5167.8 1042.78  5196.1 1043.64  5219.1  1044.9  5290.8 1045.04
    5372 1042.94  5413.7 1042.87  5529.7 1045.63  5598.1 1047.12  5721.1 1052.02
#Mann= 5 ,-1 , 0
  4262.6     .05       0  5006.4     .03       0  5011.3     .05       0
  5196.1     .12       0  5529.7     .05       0
Bank Sta=5006.4,5011.3
XS Rating Curve= 0 ,0
Exp/Cntr=0.3,0.1

Type RM Length L Ch R = 1 ,15897   ,488,488,488
BEGIN DESCRIPTION:
HARRIS BRANCH 30.0
END DESCRIPTION:
XS GIS Cut Line= 3
      2861905.68     10259503.11      2861628.25       10259466.
      2860855.66     10259453.11
#Sta/Elev= 30
  4720.1 1048.78  4790.7 1044.13    4814 1042.11  4871.4 1039.33  4910.1  1039.2
    4932 1039.39  4962.2  1038.3  4980.7    1037  4985.8 1035.56    4990 1035.29
  4990.4 1034.79  4994.6 1034.79    4995 1035.29  5052.6 1037.49  5062.6 1037.66
  5072.6 1037.02  5082.6 1038.04  5092.6 1038.26  5152.6 1038.68  5192.6 1035.94
  5242.6 1035.94  5252.6 1036.25  5272.6 1038.27  5292.6 1039.53  5355.4 1040.36
  5522.6 1041.22  5572.6 1041.94  5622.7 1043.31  5752.4 1048.51  5772.7 1049.01
#Mann= 7 ,-1 , 0
  4720.1     .05       0    4814     .12       0  4910.1     .05       0
    4990     .03       0    4995     .05       0  5355.4     .12       0
  5752.4     .05       0
Bank Sta=4990,4995
XS Rating Curve= 0 ,0
Exp/Cntr=0.3,0.1

Type RM Length L Ch R = 1 ,15409   ,499,499,499
BEGIN DESCRIPTION:
HARRIS BRANCH 29.0
END DESCRIPTION:
XS GIS Cut Line= 3
      2862005.72     10259153.11      2861820.25       10259160.
      2860705.65     10259453.12
#Sta/Elev= 30
  4814.4 1049.95  4844.5 1048.96  4884.5 1042.82  4891.4 1042.75  4914.5 1044.03
  4949.3 1042.34  4990.4 1033.28  4992.1 1033.07  4992.4 1032.57  4997.1 1033.07
  4999.8 1034.63  5025.4 1034.63  5031.2 1035.92  5036.4 1034.89  5097.8 1036.87
  5118.5  1036.3  5147.1 1037.17  5152.2 1036.44  5201.2 1037.79  5299.9 1038.04
  5498.5 1038.23  5568.6 1039.08  5707.8 1039.82  5759.5 1041.01  5933.2 1048.52
  5938.4    1048  5973.5 1049.98  5984.4 1049.75    6049 1051.71  6152.5  1052.9
#Mann= 9 ,-1 , 0
  4814.4     .05       0  4891.4     .12       0  4990.4     .05       0
  4992.1     .03       0  4997.1     .05       0  5299.9     .12       0
  5498.5     .05       0  5568.6     .12       0  5984.4     .05       0
Bank Sta=4992.1,4997.1
XS Rating Curve= 0 ,0
Exp/Cntr=0.3,0.1

Type RM Length L Ch R = 1 ,14910   ,480,480,480
BEGIN DESCRIPTION:
HARRIS BRANCH 28.0
END DESCRIPTION:
XS GIS Cut Line= 3
      2862155.66      10258853.1       2861792.5       10258691.
      2860705.71     10259403.09
#Sta/Elev= 30
  4602.3    1048    4657 1047.53  4686.3 1046.03  4777.5 1043.13  4807.8 1041.06
  4831.1 1040.28  4836.5 1040.73  4906.2 1037.22  4958.1  1035.6  4974.6 1034.25
  4995.5 1030.62  5011.1 1030.03  5011.4 1029.53  5015.7 1029.53  5016.1 1030.03
  5020.1 1031.74    5101 1034.88  5179.3 1035.26    5195 1034.49  5260.9 1034.33
  5366.8 1034.46  5417.5 1035.39  5432.6 1034.56  5462.5 1035.88  5605.9 1035.61
    5722 1038.44  5809.2 1039.25  5851.7 1040.28  6141.1 1051.36  6299.3 1053.61
#Mann= 5 ,-1 , 0
  4602.3     .05       0  5011.1     .05       0  5016.1     .05       0
    5195     .12       0  5260.9     .05       0
Bank Sta=5011.1,5016.1
XS Rating Curve= 0 ,0
Exp/Cntr=0.3,0.1

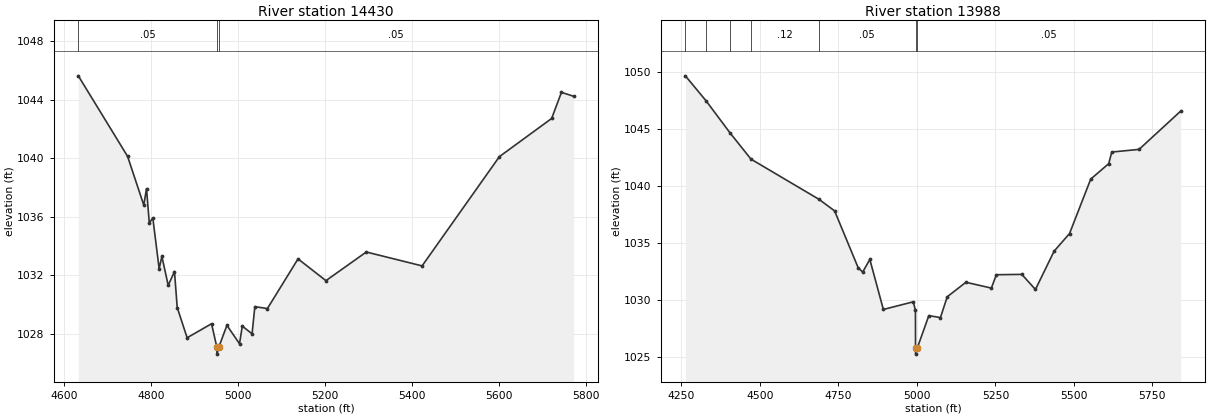
Type RM Length L Ch R = 1 ,14430   ,442,442,442
BEGIN DESCRIPTION:
HARRIS BRANCH 27.0
END DESCRIPTION:
XS GIS Cut Line= 3
      2861855.69     10258253.11      2861562.75       10258476.
       2860955.7      10258953.1
#Sta/Elev= 30
  4631.9 1045.64  4745.3 1040.13  4782.6 1036.79  4788.9 1037.92  4795.3 1035.56
  4803.4 1035.92    4818 1032.44  4824.3 1033.28  4838.8  1031.3  4853.3 1032.24
  4859.6 1029.78  4882.4 1027.71  4938.6 1028.67  4950.6 1027.09    4951 1026.59
  4955.6 1027.09    4974 1028.56    5003  1027.3  5009.4 1028.51  5031.9 1027.98
  5038.3 1029.84  5067.2 1029.71  5137.7 1033.11  5201.9 1031.62  5294.9 1033.58
  5423.3 1032.63  5601.3 1040.11  5721.5 1042.72  5744.1 1044.51  5772.1 1044.24
#Mann= 3 ,-1 , 0
  4631.9     .05       0  4950.6     .05       0  4955.6     .05       0
Bank Sta=4950.6,4955.6
XS Rating Curve= 0 ,0
Exp/Cntr=0.3,0.1

Type RM Length L Ch R = 1 ,13988   ,477,477,477
BEGIN DESCRIPTION:
HARRIS BRANCH 26.0
END DESCRIPTION:
XS GIS Cut Line= 3
      2861905.64     10257903.13      2861265.75       10258270.
      2860855.69     10259003.11
#Sta/Elev= 30
  4262.4 1049.63  4328.5 1047.44  4404.9 1044.63  4471.4 1042.34  4688.1 1038.82
  4737.8 1037.81  4812.6 1032.85  4827.2 1032.45    4850 1033.56  4893.1 1029.18
  4988.5 1029.85  4995.3 1029.09  4995.6 1025.77    4996 1025.27  5000.7 1025.77
  5037.9 1028.64  5074.9 1028.47  5096.6 1030.29    5156 1031.56  5237.1 1031.05
  5253.1 1032.22  5334.1 1032.25  5377.5 1030.93  5436.9 1034.28    5486 1035.82
  5553.6 1040.59  5610.8 1041.94  5620.7 1042.96  5707.5 1043.19    5840 1046.54
#Mann= 7 ,-1 , 0
  4262.4     .05       0  4328.5     .12       0  4404.9     .05       0
  4471.4     .12       0  4688.1     .05       0  4995.6     .03       0
  5000.7     .05       0
Bank Sta=4995.6,5000.7
XS Rating Curve= 0 ,0
Exp/Cntr=0.3,0.1