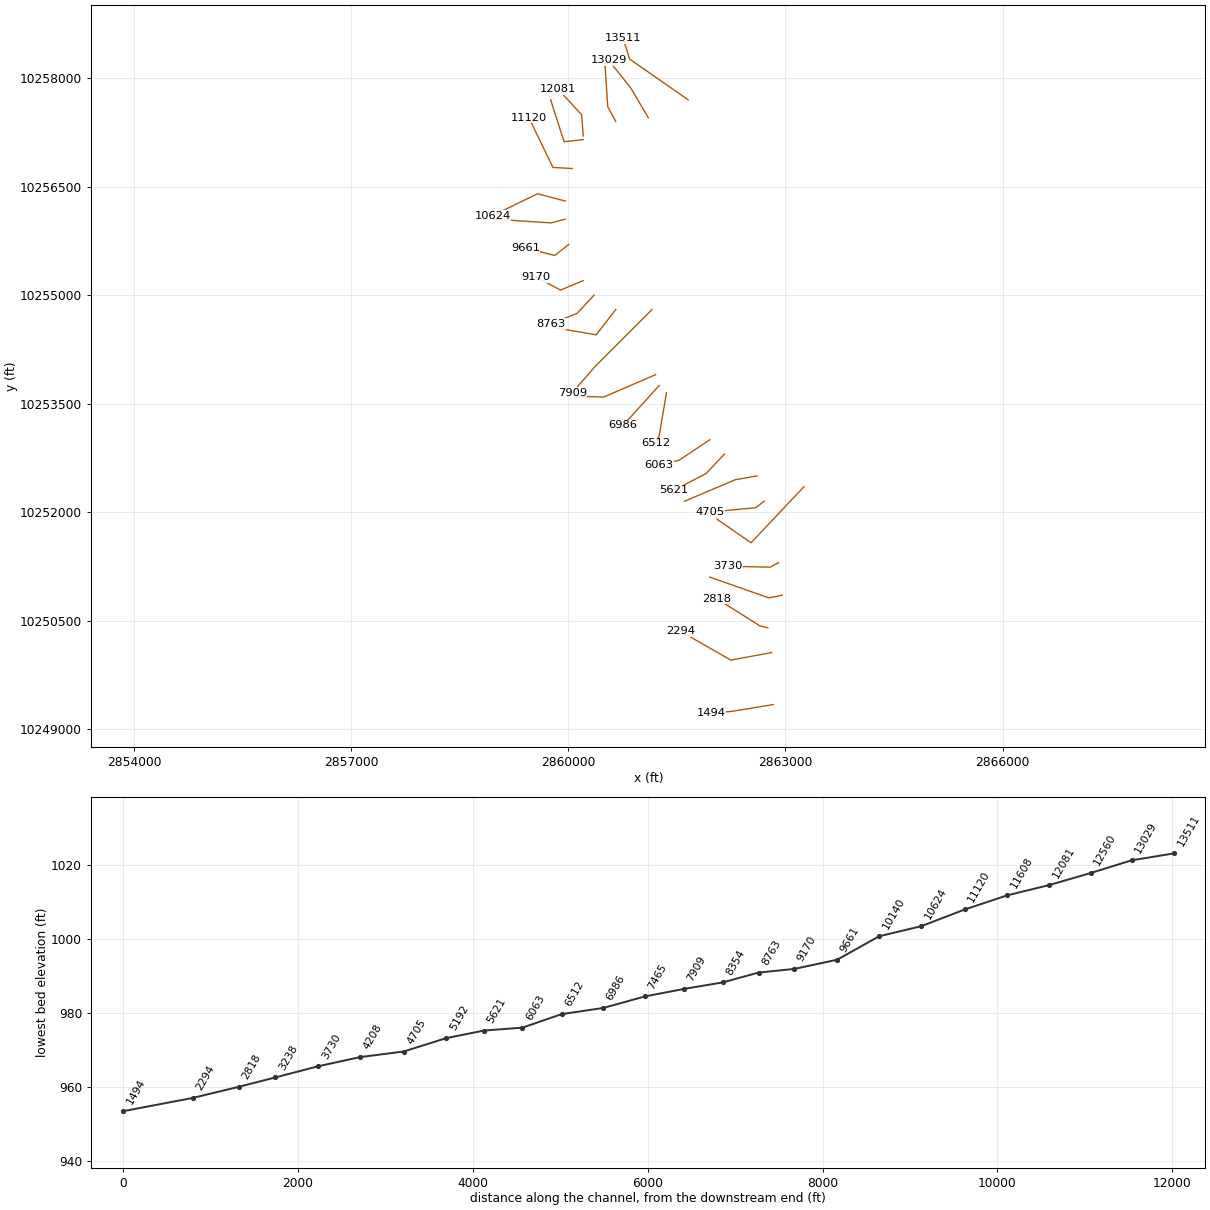
HEC-RAS study HARRIS BRANCH.prj: HARRIS BRANCH Base Level Engineering

--- HARRIS BRANCH.g01 (geometry) --- (continued)

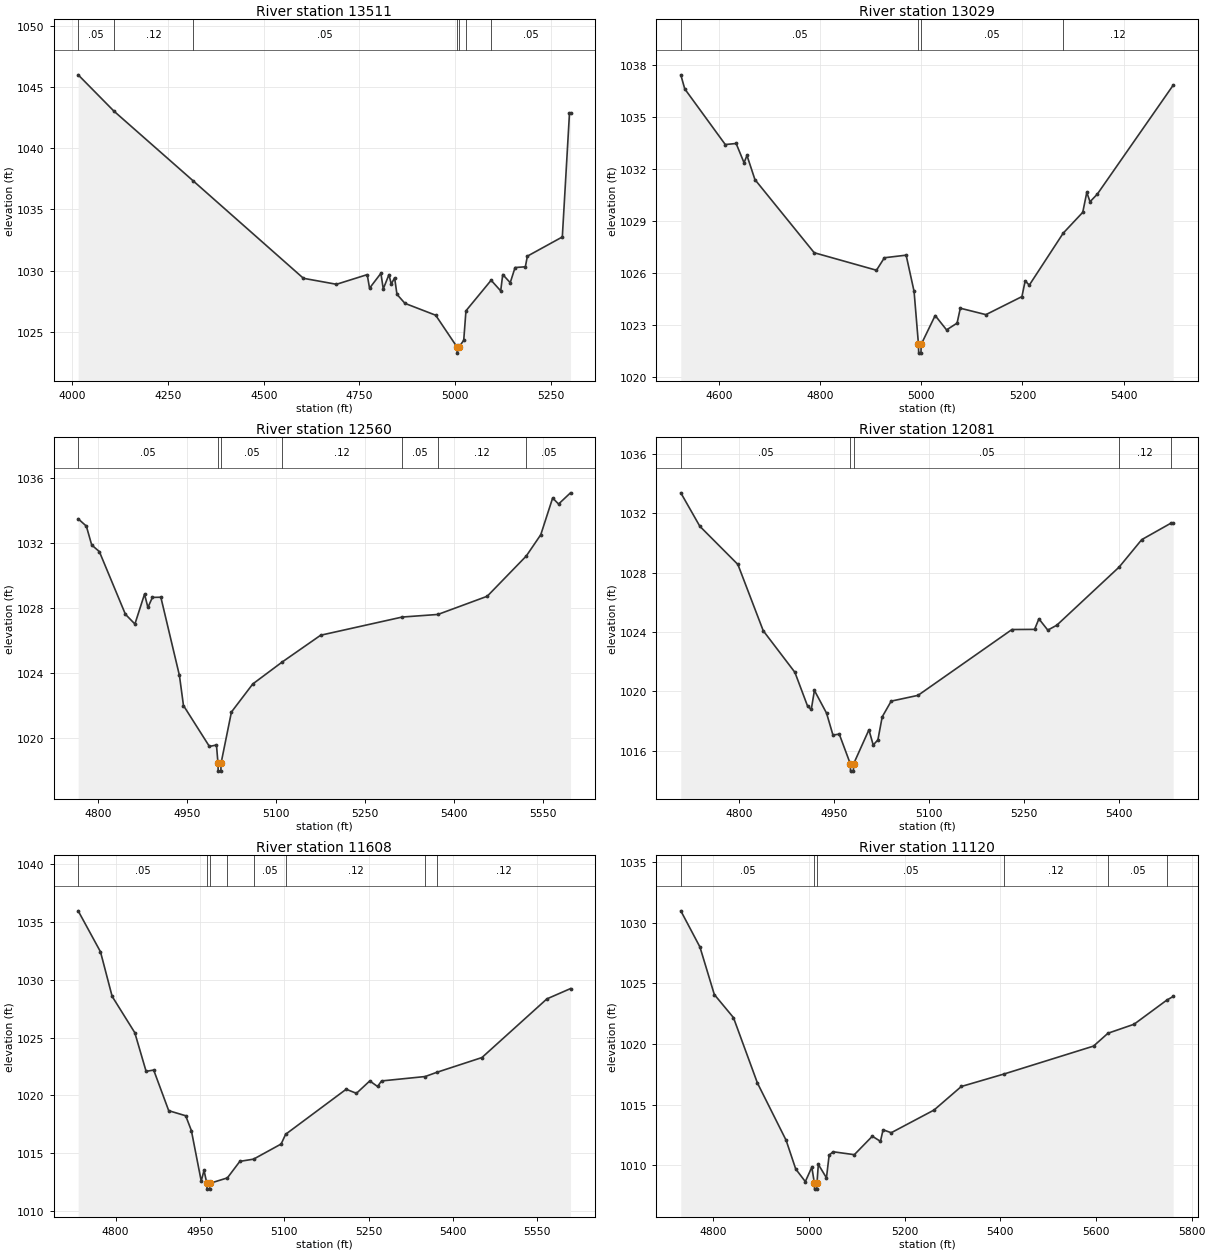
Type RM Length L Ch R = 1 ,13511   ,482,482,482
BEGIN DESCRIPTION:
HARRIS BRANCH 25.0
END DESCRIPTION:
XS GIS Cut Line= 3
      2861655.69     10257703.11      2860847.25       10258266.
      2860755.67     10258553.15
#Sta/Elev= 30
  4014.9 1046.01  4108.1 1043.05  4315.4 1037.34  4603.5 1029.37  4689.9 1028.88
  4770.2 1029.67  4776.3 1028.56    4806 1029.78  4812.1  1028.5    4827 1029.67
    4833  1028.9  4841.8 1029.41  4847.9 1028.06  4868.8 1027.32  4949.1 1026.35
  5004.9 1023.75  5005.3 1023.25  5010.1 1023.75  5022.4  1024.3  5028.2 1026.71
    5094 1029.21    5119 1028.34  5124.3 1029.68  5143.9 1029.01  5156.5 1030.25
  5183.4 1030.31  5188.7 1031.18    5280 1032.75  5298.7 1042.86  5301.4 1042.86
#Mann= 7 ,-1 , 0
  4014.9     .05       0  4108.1     .12       0  4315.4     .05       0
  5004.9     .05       0  5010.1     .05       0  5028.2     .12       0
    5094     .05       0
Bank Sta=5004.9,5010.1
XS Rating Curve= 0 ,0
Exp/Cntr=0.3,0.1

Type RM Length L Ch R = 1 ,13029   ,469,469,469
BEGIN DESCRIPTION:
HARRIS BRANCH 24.0
END DESCRIPTION:
XS GIS Cut Line= 3
      2861105.67     10257453.14        2860865.       10257863.
      2860555.66     10258253.14
#Sta/Elev= 30
  4524.7 1037.43  4532.5 1036.62  4612.6 1033.41  4634.1 1033.47  4649.7 1032.36
  4655.5 1032.78  4671.2 1031.39  4788.4 1027.17  4911.5 1026.16  4927.1 1026.88
  4970.1 1027.03  4985.8 1024.94  4994.5 1021.88  4994.9 1021.38  4999.4 1021.38
  4999.8 1021.88  5027.5 1023.55    5050 1022.72  5070.8 1023.11  5077.2 1023.97
  5127.8  1023.6    5199 1024.64  5205.4 1025.55  5213.5  1025.3  5280.6  1028.3
  5319.2  1029.5  5327.2 1030.65  5333.6 1030.11    5348 1030.55  5497.9 1036.83
#Mann= 4 ,-1 , 0
  4524.7     .05       0  4994.5     .03       0  4999.8     .05       0
  5280.6     .12       0
Bank Sta=4994.5,4999.8
XS Rating Curve= 0 ,0
Exp/Cntr=0.3,0.1

Type RM Length L Ch R = 1 ,12560   ,479,479,479
BEGIN DESCRIPTION:
HARRIS BRANCH 23.0
END DESCRIPTION:
XS GIS Cut Line= 3
      2860655.69     10257403.11      2860544.75       10257608.
      2860505.68     10258203.12
#Sta/Elev= 30
    4767 1033.48  4780.8 1033.03  4789.8 1031.87  4802.7 1031.46  4846.6  1027.6
  4862.6    1027  4878.8 1028.84  4884.5 1028.02  4892.1 1028.64  4906.3 1028.65
  4937.6 1023.83  4944.4 1021.98  4988.1 1019.46    5000 1019.55  5002.5 1018.44
  5002.9 1017.94  5007.4 1017.94  5007.8 1018.44  5025.2 1021.58  5061.2 1023.31
  5110.7 1024.66  5175.5 1026.31  5312.9 1027.43  5373.1 1027.59  5456.1 1028.71
  5521.9 1031.19  5546.3  1032.5  5566.3 1034.76  5576.3 1034.39  5596.4 1035.08
#Mann= 7 ,-1 , 0
    4767     .05       0  5002.5     .03       0  5007.8     .05       0
  5110.7     .12       0  5312.9     .05       0  5373.1     .12       0
  5521.9     .05       0
Bank Sta=5002.5,5007.8
XS Rating Curve= 0 ,0
Exp/Cntr=0.3,0.1

Type RM Length L Ch R = 1 ,12081   ,473,473,473
BEGIN DESCRIPTION:
HARRIS BRANCH 22.0
END DESCRIPTION:
XS GIS Cut Line= 3
      2860205.69     10257203.07       2860184.5       10257495.
      2859855.67     10257853.13
#Sta/Elev= 30
  4707.3 1033.37  4737.4 1031.12  4797.6 1028.55  4837.7 1024.09  4887.8 1021.29
  4907.9 1019.01  4913.7 1018.79  4918.7 1020.07  4937.9 1018.54    4948 1017.07
    4958 1017.13  4975.4 1015.14  4975.8 1014.64  4980.3 1014.64  4980.8 1015.14
  5004.9 1017.42  5011.7  1016.4  5019.1 1016.74  5025.9 1018.29  5040.1 1019.35
  5082.6 1019.74  5231.2 1024.17    5267 1024.18  5273.8 1024.89  5287.9 1024.13
  5302.1 1024.46  5400.9 1028.38  5436.5 1030.22  5483.2 1031.34  5486.2 1031.34
#Mann= 5 ,-1 , 0
  4707.3     .05       0  4975.4     .05       0  4980.8     .05       0
  5400.9     .12       0  5483.2     .05       0
Bank Sta=4975.4,4980.8
XS Rating Curve= 0 ,0
Exp/Cntr=0.3,0.1

Type RM Length L Ch R = 1 ,11608   ,488,488,488
BEGIN DESCRIPTION:
HARRIS BRANCH 21.0
END DESCRIPTION:
XS GIS Cut Line= 3
      2860205.69     10257153.11        2859941.       10257123.
      2859755.68     10257703.12
#Sta/Elev= 30
  4733.6 1035.95  4773.3 1032.41    4794 1028.56  4834.3 1025.42  4854.4 1022.08
  4867.9 1022.19  4894.6 1018.68  4924.8 1018.24  4934.9 1016.96  4952.4  1012.6
  4957.4 1013.52  4962.4  1012.4  4962.8  1011.9  4967.4  1011.9  4967.8  1012.4
  4998.9 1012.87  5021.1  1014.3  5045.4 1014.49  5094.5  1015.8  5102.5 1016.64
  5210.1 1020.53  5228.4 1020.18  5252.1 1021.25  5265.9 1020.77  5273.1 1021.25
  5350.6 1021.63    5371 1021.99  5451.5 1023.27    5567 1028.34    5609 1029.23
#Mann= 8 ,-1 , 0
  4733.6     .05       0  4962.4     .07       0  4967.8     .05       0
  4998.9     .12       0  5045.4     .05       0  5102.5     .12       0
  5350.6     .05       0    5371     .12       0
Bank Sta=4962.4,4967.8
XS Rating Curve= 0 ,0
Exp/Cntr=0.3,0.1

Type RM Length L Ch R = 1 ,11120   ,496,496,496
BEGIN DESCRIPTION:
HARRIS BRANCH 20.0
END DESCRIPTION:
XS GIS Cut Line= 3
      2860055.64     10256753.11      2859787.75       10256768.
       2859455.7     10257453.07
#Sta/Elev= 30
  4731.7 1030.99  4771.7 1028.01  4801.8 1024.09  4841.8 1022.19  4891.9  1016.8
    4952 1012.07    4972 1009.71  4992.1 1008.67  5005.7 1009.86    5011 1008.55
  5011.4 1008.05    5016 1008.05  5016.5 1008.55  5019.3 1010.09  5036.3 1008.98
  5041.9 1010.85  5050.1 1011.13  5094.6 1010.89  5132.2 1012.41  5149.2 1011.99
  5154.7 1012.94  5171.8  1012.7  5261.3 1014.57  5318.3 1016.51  5407.7 1017.54
  5594.8 1019.84    5625  1020.9  5679.5 1021.64    5748 1023.63  5761.3 1023.93
#Mann= 6 ,-1 , 0
  4731.7     .05       0    5011     .05       0  5016.5     .05       0
  5407.7     .12       0    5625     .05       0    5748     .12       0
Bank Sta=5011,5016.5
XS Rating Curve= 0 ,0
Exp/Cntr=0.3,0.1

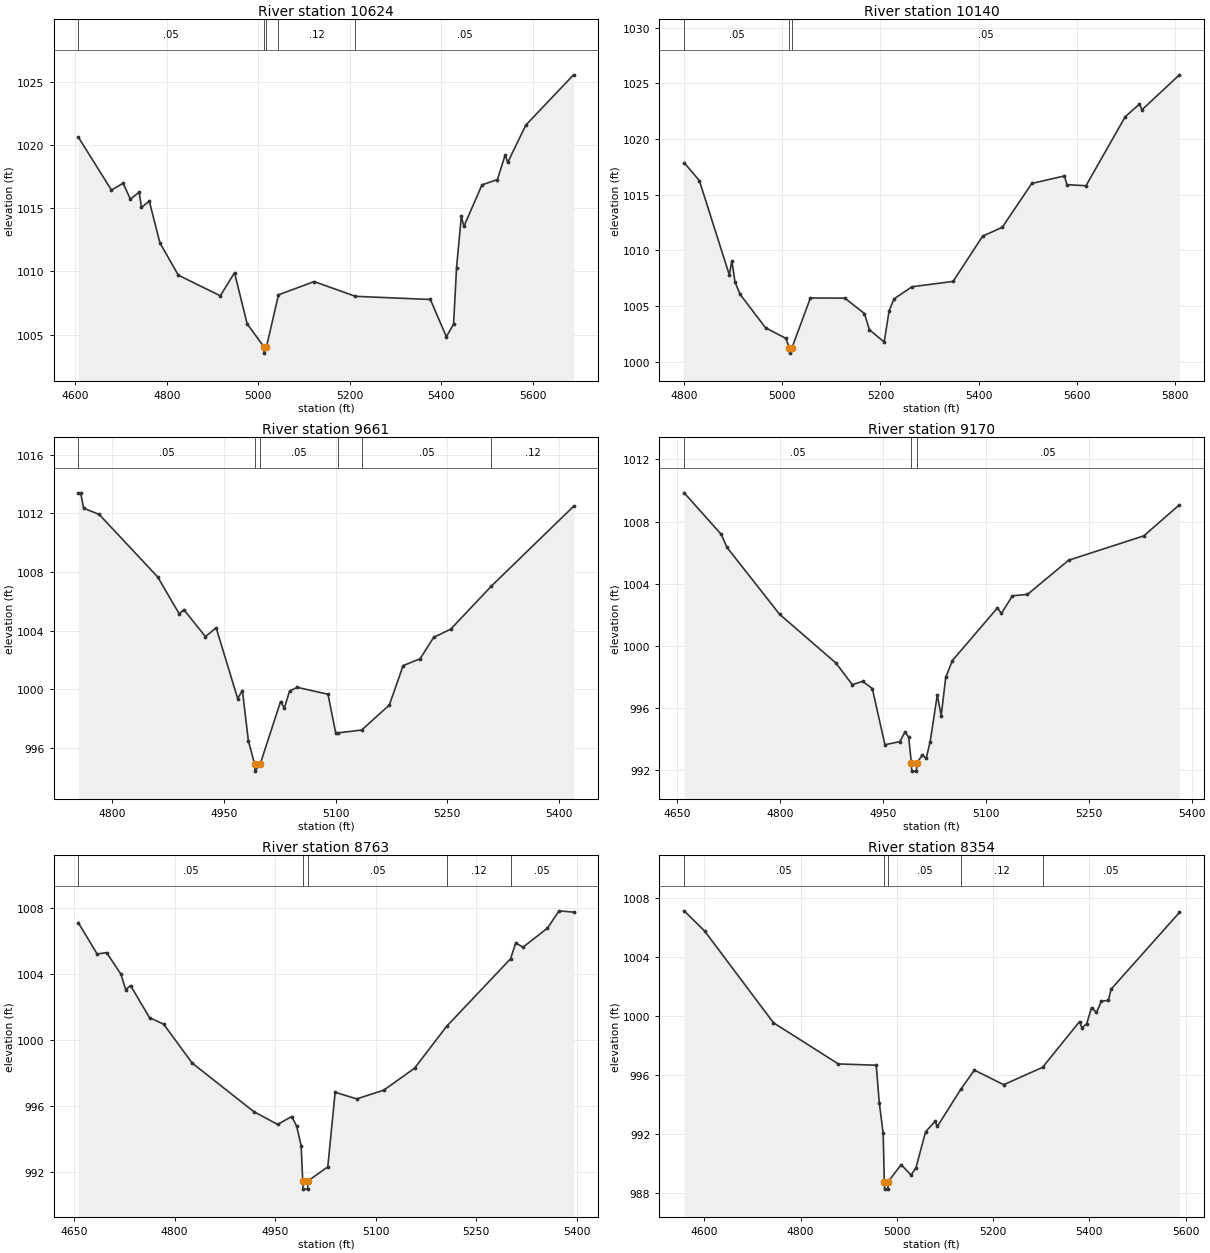
Type RM Length L Ch R = 1 ,10624   ,484,484,484
BEGIN DESCRIPTION:
HARRIS BRANCH 19.0
END DESCRIPTION:
XS GIS Cut Line= 3
       2859955.7     10256303.11      2859575.25       10256404.
      2858955.65      10256103.1
#Sta/Elev= 30
  4606.4 1020.65  4678.8 1016.45  4704.3 1016.99  4720.2 1015.73  4739.3 1016.28
  4744.5 1015.08  4761.6 1015.57  4784.7 1012.27  4824.9 1009.71  4916.8 1008.07
  4947.8  1009.9  4975.4 1005.85  5012.1 1004.03  5012.5 1003.53  5017.6 1004.03
  5043.9 1008.15  5121.8  1009.2  5212.2 1008.03  5375.8 1007.78  5410.8 1004.83
  5426.5 1005.82  5433.1 1010.31  5443.5  1014.4  5449.1 1013.57  5488.6 1016.86
  5522.3 1017.28  5539.3 1019.23  5544.9 1018.64  5584.5  1021.6  5688.8 1025.58
#Mann= 5 ,-1 , 0
  4606.4     .05       0  5012.1     .05       0  5017.6     .05       0
  5043.9     .12       0  5212.2     .05       0
Bank Sta=5012.1,5017.6
XS Rating Curve= 0 ,0
Exp/Cntr=0.3,0.1

Type RM Length L Ch R = 1 ,10140   ,479,479,479
BEGIN DESCRIPTION:
HARRIS BRANCH 18.0
END DESCRIPTION:
XS GIS Cut Line= 3
      2859955.64      10256053.1      2859762.75       10256001.
      2858955.73     10256053.11
#Sta/Elev= 30
  4800.2 1017.88  4831.2 1016.27  4892.1 1007.81  4897.3 1009.08  4903.7 1007.17
  4914.1 1006.06  4965.9 1003.06  5007.1 1002.11  5014.4 1001.28  5014.8 1000.78
  5019.9 1001.28  5057.2 1005.73  5127.3 1005.72  5167.4 1004.33  5177.4 1002.88
  5207.5 1001.78  5217.5 1004.57  5227.5 1005.65  5264.1 1006.74  5347.8 1007.22
  5407.9 1011.28    5448 1012.08  5508.1 1016.02  5574.6 1016.69  5579.6 1015.91
  5618.4 1015.81  5698.5 1022.02  5727.4 1023.14  5732.4 1022.63  5808.7 1025.77
#Mann= 3 ,-1 , 0
  4800.2     .05       0  5014.4     .03       0  5019.9     .05       0
Bank Sta=5014.4,5019.9
XS Rating Curve= 0 ,0
Exp/Cntr=0.3,0.1

Type RM Length L Ch R = 1 ,9661    ,491,491,491
BEGIN DESCRIPTION:
HARRIS BRANCH 17.0
END DESCRIPTION:
XS GIS Cut Line= 3
       2860005.7     10255703.12      2859812.75       10255551.
      2859405.66     10255653.12
#Sta/Elev= 30
  4754.3  1013.4  4757.5  1013.4  4761.5 1012.35  4782.3 1011.93  4860.9 1007.67
  4889.8 1005.16  4896.2 1005.43  4925.1  1003.6  4939.5  1004.2  4968.4  999.38
  4974.8  999.92  4982.8   996.5  4991.1  994.93  4991.6  994.43  4998.8  994.93
    5026  999.17  5031.1  998.73  5038.2  999.89  5048.5 1000.14  5089.8  999.67
  5100.1  997.03  5103.6  997.04    5135  997.23  5172.2  998.94  5190.7 1001.62
  5213.5 1002.09  5231.8 1003.55  5254.7 1004.11  5309.4 1007.05  5419.7 1012.48
#Mann= 6 ,-1 , 0
  4754.3     .05       0  4991.1     .05       0  4998.8     .05       0
  5103.6     .12       0    5135     .05       0  5309.4     .12       0
Bank Sta=4991.1,4998.8
XS Rating Curve= 0 ,0
Exp/Cntr=0.3,0.1

Type RM Length L Ch R = 1 ,9170    ,407,407,407
BEGIN DESCRIPTION:
HARRIS BRANCH 16.0
END DESCRIPTION:
XS GIS Cut Line= 3
      2860205.73     10255203.13      2859892.25       10255072.
      2859555.69     10255253.11
#Sta/Elev= 30
  4660.2 1009.85  4714.4 1007.17  4722.4 1006.35  4799.3 1002.03  4881.5  998.89
  4905.3   997.5  4920.4  997.71  4934.5  997.25  4952.9  993.63  4974.6  993.83
  4982.1  994.45  4987.5  994.12  4991.5  992.43    4992  991.93  4998.8  991.93
  4999.3  992.43  5007.3  992.97    5013  992.75  5018.8  993.82  5029.2  996.83
  5034.9   995.5  5041.5  997.96  5051.2  999.05  5116.9 1002.44  5122.6 1002.08
  5138.8 1003.22  5160.7 1003.31  5220.7 1005.51  5330.3 1007.08  5382.2 1009.08
#Mann= 3 ,-1 , 0
  4660.2     .05       0  4991.5     .05       0  4999.3     .05       0
Bank Sta=4991.5,4999.3
XS Rating Curve= 0 ,0
Exp/Cntr=0.3,0.1

Type RM Length L Ch R = 1 ,8763    ,409,409,409
BEGIN DESCRIPTION:
HARRIS BRANCH 15.0
END DESCRIPTION:
XS GIS Cut Line= 3
      2860355.69     10255003.12      2860122.25       10254751.
      2859755.66      10254603.1
#Sta/Elev= 30
  4656.4 1007.13  4684.5 1005.23  4698.7 1005.31  4720.2 1003.99    4727 1003.07
  4734.4 1003.31  4762.7 1001.36  4783.7 1000.97  4826.2  998.61  4918.1  995.66
  4953.8  994.88  4974.8  995.36  4982.1  994.78  4988.9  993.58  4991.2  991.45
  4991.7  990.95  4998.6  990.95  4999.1  991.45  5028.6   992.3  5039.6  996.83
  5071.8  996.43  5112.1  996.96    5158  998.29    5206 1000.84  5301.3 1004.94
    5309  1005.9  5319.8 1005.64  5356.4  1006.8  5373.7 1007.85  5395.3 1007.77
#Mann= 5 ,-1 , 0
  4656.4     .05       0  4991.2     .05       0  4999.1     .05       0
    5206     .12       0  5301.3     .05       0
Bank Sta=4991.2,4999.1
XS Rating Curve= 0 ,0
Exp/Cntr=0.3,0.1

Type RM Length L Ch R = 1 ,8354    ,445,445,445
BEGIN DESCRIPTION:
HARRIS BRANCH 14.0
END DESCRIPTION:
XS GIS Cut Line= 3
      2860655.71     10254803.14       2860384.5       10254454.
      2859805.72      10254553.1
#Sta/Elev= 30
  4557.9 1007.16  4600.5 1005.79  4743.5  999.57  4878.3  996.78  4957.1  996.69
  4963.4  994.16  4971.5  992.07  4973.9  988.79  4974.4  988.29  4981.3  988.29
  4981.8  988.79  5008.9  989.95  5029.3  989.25  5039.4  989.71  5059.7  992.18
  5079.3  992.88  5084.3  992.55    5133  995.07  5161.1  996.36    5222  995.37
  5302.8  996.55  5379.6  999.65  5384.6  999.22  5394.5  999.51  5404.6  1000.6
  5414.8 1000.27  5424.9 1001.02  5439.6  1001.1  5445.2 1001.85  5587.2 1007.05
#Mann= 5 ,-1 , 0
  4557.9     .05       0  4973.9     .03       0  4981.8     .05       0
    5133     .12       0  5302.8     .05       0
Bank Sta=4973.9,4981.8
XS Rating Curve= 0 ,0
Exp/Cntr=0.3,0.1

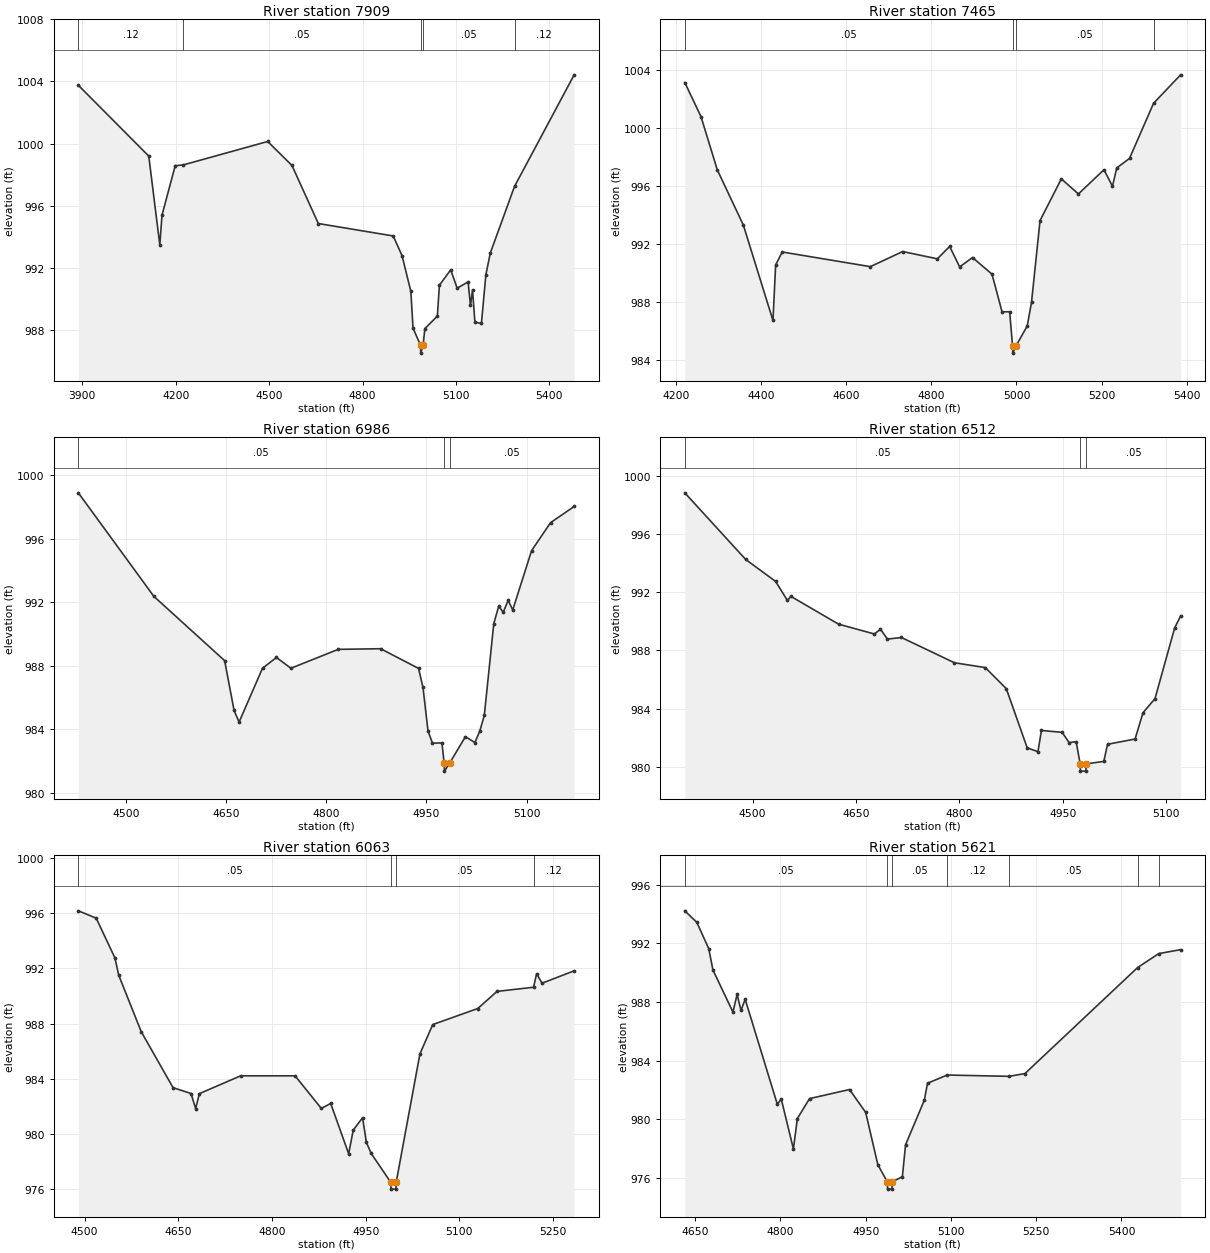
Type RM Length L Ch R = 1 ,7909    ,444,444,444
BEGIN DESCRIPTION:
HARRIS BRANCH 13.0
END DESCRIPTION:
XS GIS Cut Line= 3
      2861155.65     10254803.08        2860369.       10254016.
       2860055.7     10253653.14
#Sta/Elev= 30
  3887.2 1003.75  4113.4  999.19  4148.8  993.48  4155.9  995.39  4198.3  998.57
  4223.7  998.62  4495.3 1000.13  4573.1  998.59  4657.9  994.85  4898.3  994.05
  4926.6  992.79  4954.9  990.49    4962  988.12  4986.2  987.01  4986.7  986.51
  4994.3  987.01    5000  988.09  5040.1  988.89  5046.7  990.88  5082.9  991.87
  5103.7  990.69  5138.8  991.09  5146.5  989.58  5153.1  990.58  5160.7   988.5
  5181.6  988.42  5195.9  991.55  5210.1  992.95  5287.9  997.24  5479.4 1004.42
#Mann= 5 ,-1 , 0
  3887.2     .12       0  4223.7     .05       0  4986.2     .05       0
  4994.3     .05       0  5287.9     .12       0
Bank Sta=4986.2,4994.3
XS Rating Curve= 0 ,0
Exp/Cntr=0.3,0.1

Type RM Length L Ch R = 1 ,7465    ,479,479,479
BEGIN DESCRIPTION:
HARRIS BRANCH 12.0
END DESCRIPTION:
XS GIS Cut Line= 3
      2861205.71     10253903.12        2860491.       10253594.
      2860105.71     10253603.11
#Sta/Elev= 30
  4221.3 1003.14  4259.3 1000.79  4297.6  997.12  4358.7  993.32  4428.3  986.74
  4434.6  990.57  4450.1  991.46  4656.9  990.45  4732.8  991.49  4814.2  990.99
  4843.2  991.84  4866.6  990.43  4896.8  991.08  4942.6  989.93  4966.1  987.34
    4984  987.34  4990.8  984.99  4991.3  984.49  4998.9  984.99  5025.3  986.36
  5035.3  987.99  5055.3  993.62  5105.3   996.5  5145.4  995.46  5205.4  997.13
  5225.4  995.99  5235.4  997.25  5265.4  997.91  5321.9 1001.71  5385.4 1003.67
#Mann= 4 ,-1 , 0
  4221.3     .05       0  4990.8     .05       0  4998.9     .05       0
  5321.9     .12       0
Bank Sta=4990.8,4998.9
XS Rating Curve= 0 ,0
Exp/Cntr=0.3,0.1

Type RM Length L Ch R = 1 ,6986    ,474,474,474
BEGIN DESCRIPTION:
HARRIS BRANCH 11.0
END DESCRIPTION:
XS GIS Cut Line= 3
      2861255.68      10253753.1        2860872.       10253329.
      2860755.68     10253203.11
#Sta/Elev= 30
  4428.1  998.88  4541.3  992.36  4647.4  988.31  4661.6  985.17  4669.1  984.44
  4704.2  987.83  4725.1  988.51  4746.8  987.83  4817.7  989.02  4881.3  989.06
  4938.1  987.82  4944.8  986.62  4952.3  983.88    4959  983.11  4973.2  983.13
  4976.5  981.85    4977  981.35  4984.7  981.85  5008.4  983.52  5022.6  983.15
  5029.9  983.87  5036.7  984.86  5050.9  990.64  5058.3  991.74  5065.1  991.36
  5072.5  992.11  5079.3   991.5  5107.6  995.24    5136     997  5171.4  998.02
#Mann= 3 ,-1 , 0
  4428.1     .05       0  4976.5     .03       0  4984.7     .05       0
Bank Sta=4976.5,4984.7
XS Rating Curve= 0 ,0
Exp/Cntr=0.3,0.1

Type RM Length L Ch R = 1 ,6512    ,449,449,449
BEGIN DESCRIPTION:
HARRIS BRANCH 10.0
END DESCRIPTION:
XS GIS Cut Line= 3
      2861355.69     10253653.12       2861256.5       10253063.
      2861205.67     10252953.08
#Sta/Elev= 30
  4401.6  998.85    4490  994.26  4533.4  992.75  4550.5  991.44  4555.6  991.72
  4624.7  989.81  4676.8  989.13  4685.5  989.46  4695.7  988.78    4716  988.89
  4792.9  987.15  4837.6  986.82  4868.1  985.37  4898.5  981.29  4914.1  981.03
  4919.1  982.49  4949.2  982.36  4959.3  981.65  4969.5  981.72  4975.3  980.19
  4975.8  979.69  4983.6  979.69  4984.1  980.19  5009.6  980.36  5015.1  981.54
    5055   981.9  5066.5  983.71  5083.9  984.68  5112.4  989.54  5121.1  990.38
#Mann= 3 ,-1 , 0
  4401.6     .05       0  4975.3     .03       0  4984.1     .05       0
Bank Sta=4975.3,4984.1
XS Rating Curve= 0 ,0
Exp/Cntr=0.3,0.1

Type RM Length L Ch R = 1 ,6063    ,442,442,442
BEGIN DESCRIPTION:
HARRIS BRANCH 9.0
END DESCRIPTION:
XS GIS Cut Line= 3
       2861955.7     10253003.12       2861531.5       10252720.
      2861255.69     10252653.11
#Sta/Elev= 30
    4490  996.16  4518.6  995.63  4548.6  992.75  4554.6  991.51  4590.6  987.42
  4641.7  983.36  4670.4  982.94  4677.8  981.85  4683.8  982.93  4749.9  984.22
    4837  984.22    4879  981.86    4894  982.22  4922.8  978.58  4930.1  980.29
  4945.1  981.19  4951.1  979.41  4958.9   978.6  4990.1  976.52  4990.6  976.02
  4998.4  976.02  4998.9  976.52  5036.9  985.81  5057.4  987.93  5129.5  989.09
  5160.3  990.33  5218.8  990.63  5223.7  991.61  5232.4  990.92  5283.8  991.82
#Mann= 4 ,-1 , 0
    4490     .05       0  4990.1     .05       0  4998.9     .05       0
  5218.8     .12       0
Bank Sta=4990.1,4998.9
XS Rating Curve= 0 ,0
Exp/Cntr=0.3,0.1

Type RM Length L Ch R = 1 ,5621    ,429,429,429
BEGIN DESCRIPTION:
HARRIS BRANCH 8.0
END DESCRIPTION:
XS GIS Cut Line= 3
      2862155.65     10252803.08      2861903.25       10252535.
      2861455.66      10252303.1
#Sta/Elev= 30
  4631.8  994.22    4653  993.43    4674  991.63  4681.3  990.18  4716.5  987.31
  4723.8  988.51  4730.7  987.42    4738  988.18  4794.6  981.01  4801.5  981.37
  4822.9  977.96  4829.8  980.04  4851.3   981.4  4921.6  982.02    4950  980.46
  4971.4  976.89    4988  975.72  4988.5  975.22  4996.3  975.22  4996.8  975.72
  5014.6  976.07  5020.2  978.25  5053.2  981.29  5058.8  982.45  5093.5  983.01
  5202.3  982.92  5230.2  983.11  5428.5  990.35  5465.6   991.3  5504.1  991.57
#Mann= 7 ,-1 , 0
  4631.8     .05       0    4988     .03       0  4996.8     .05       0
  5093.5     .12       0  5202.3     .05       0  5428.5     .12       0
  5465.6     .05       0
Bank Sta=4988,4996.8
XS Rating Curve= 0 ,0
Exp/Cntr=0.3,0.1

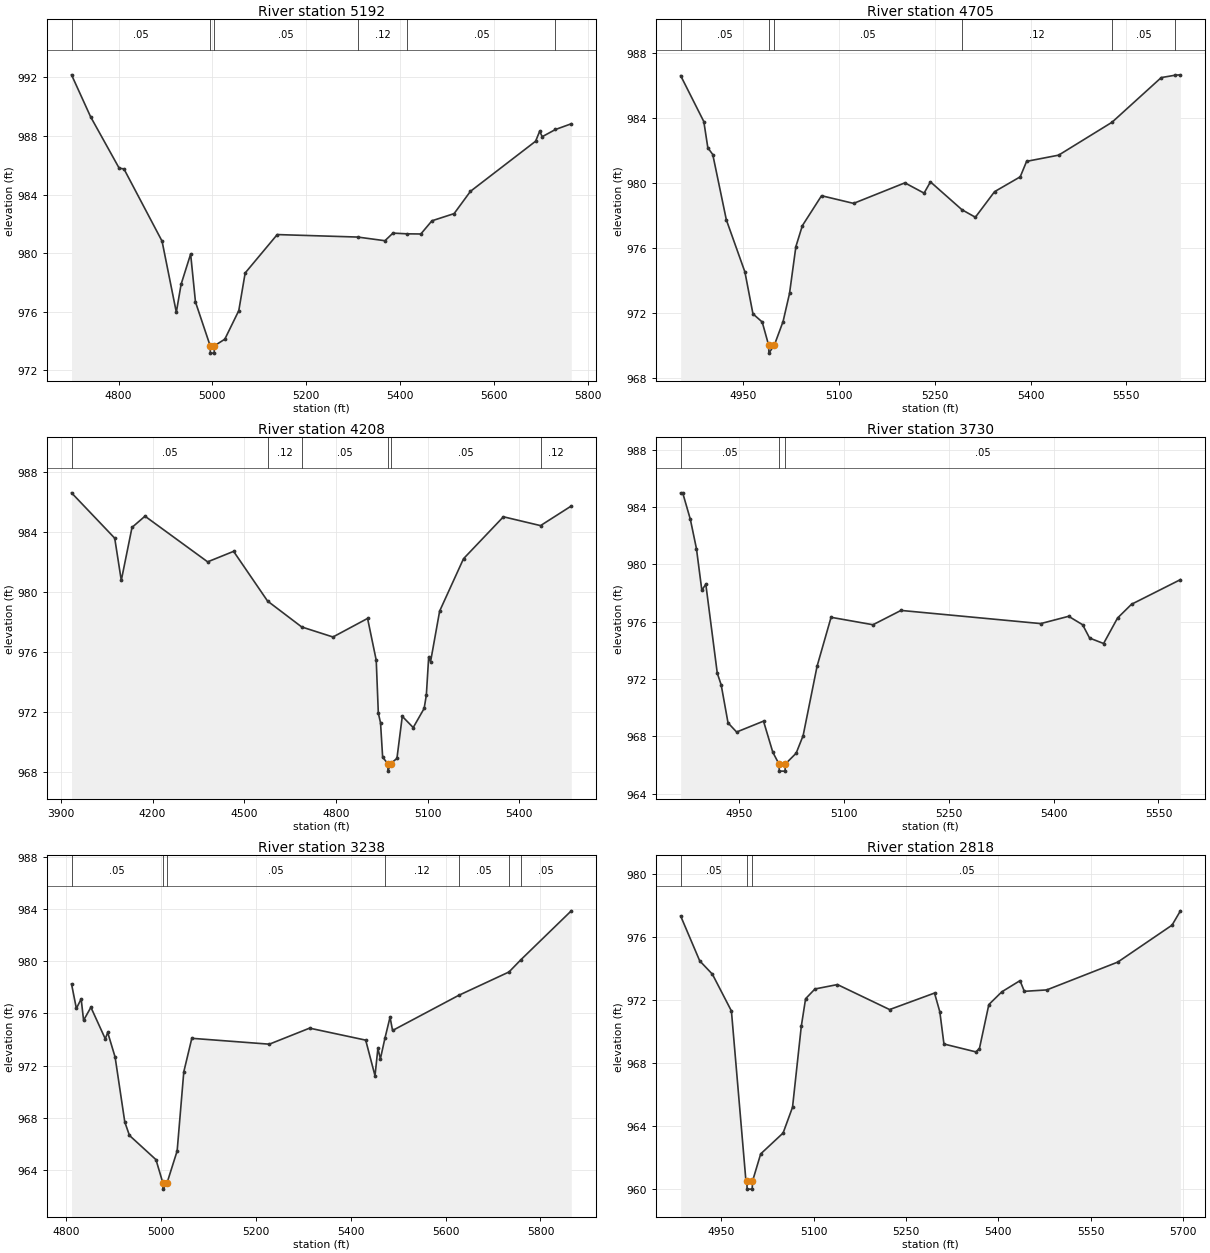
Type RM Length L Ch R = 1 ,5192    ,487,487,487
BEGIN DESCRIPTION:
HARRIS BRANCH 7.0
END DESCRIPTION:
XS GIS Cut Line= 3
      2862605.64      10252503.1        2862310.       10252451.
       2861605.7     10252153.12
#Sta/Elev= 30
  4699.8  992.17  4740.4  989.31  4801.3   985.8  4811.5  985.75  4892.7  980.82
  4923.1  975.97  4933.3  977.88  4953.6  979.94  4963.9  976.67  4995.2  973.68
  4995.7  973.18  5003.7  973.18  5004.2  973.68  5026.4  974.13  5056.2  976.08
  5069.8  978.65  5138.1  981.27  5309.7   981.1  5367.6  980.85  5384.7  981.37
    5415  981.32  5444.1  981.31  5467.8  982.21    5515   982.7  5549.8  984.22
  5688.7  987.64  5697.3  988.32  5702.8  987.95    5731  988.44  5764.7  988.83
#Mann= 6 ,-1 , 0
  4699.8     .05       0  4995.2     .03       0  5004.2     .05       0
  5309.7     .12       0    5415     .05       0    5731     .12       0
Bank Sta=4995.2,5004.2
XS Rating Curve= 0 ,0
Exp/Cntr=0.3,0.1

Type RM Length L Ch R = 1 ,4705    ,497,497,497
BEGIN DESCRIPTION:
HARRIS BRANCH 6.0
END DESCRIPTION:
XS GIS Cut Line= 3
      2862705.67      10252153.1      2862587.75       10252063.
      2861955.68     10252003.11
#Sta/Elev= 30
  4851.6  986.58  4887.9  983.76  4894.2  982.15  4901.9  981.74  4923.2  977.73
  4952.3  974.53  4964.9  971.96  4979.4  971.46  4989.4  970.05  4989.9  969.55
  4998.5  970.05  5012.1  971.49  5022.2  973.21  5032.2  976.09  5042.3  977.37
  5072.4  979.21  5122.6  978.74    5203     980  5233.1  979.37  5243.1  980.06
  5292.5  978.35  5313.5  977.89  5343.6  979.46  5383.8  980.37  5393.8  981.32
    5444   981.7  5527.7  983.72  5604.8  986.46  5627.1  986.61  5634.9  986.63
#Mann= 6 ,-1 , 0
  4851.6     .05       0  4989.4     .03       0  4998.5     .05       0
  5292.5     .12       0  5527.7     .05       0  5627.1     .12       0
Bank Sta=4989.4,4998.5
XS Rating Curve= 0 ,0
Exp/Cntr=0.3,0.1

Type RM Length L Ch R = 1 ,4208    ,478,478,478
BEGIN DESCRIPTION:
HARRIS BRANCH 5.0
END DESCRIPTION:
XS GIS Cut Line= 3
      2863255.69     10252353.12      2862524.75       10251578.
       2862055.7      10251903.1
#Sta/Elev= 30
  3934.6  986.63    4076   983.6  4097.5  980.78  4132.6  984.32  4175.1  985.07
  4380.2  982.02  4465.2  982.72  4576.4   979.4  4688.2  977.67  4790.5     977
  4903.8  978.24  4932.1  975.45    4939  971.91  4946.2  971.27  4953.1  968.97
    4970  968.54  4970.5  968.04  4979.2  968.54  4999.9  968.89  5017.4   971.7
  5053.2  970.95    5089  972.23  5096.2  973.12  5103.9  975.68    5110  975.35
  5139.7  978.73  5217.9  982.23  5348.5  985.03    5470  984.44  5570.7  985.75
#Mann= 6 ,-1 , 0
  3934.6     .05       0  4576.4     .12       0  4688.2     .05       0
    4970     .03       0  4979.2     .05       0    5470     .12       0
Bank Sta=4970,4979.2
XS Rating Curve= 0 ,0
Exp/Cntr=0.3,0.1

Type RM Length L Ch R = 1 ,3730    ,492,492,492
BEGIN DESCRIPTION:
HARRIS BRANCH 4.0
END DESCRIPTION:
XS GIS Cut Line= 3
      2862905.72     10251303.13        2862787.       10251241.
      2862205.73     10251253.11
#Sta/Elev= 30
    4866     985  4868.9     985  4879.9  983.14  4888.6   981.1  4896.3   978.2
    4902  978.62  4918.4  972.41    4924  971.59  4933.8  968.94  4946.1   968.3
  4984.6  969.06  4997.9  966.89  5006.7  966.07  5007.2  965.57  5015.4  965.57
  5015.9  966.07  5031.3  966.82  5041.3  968.05  5061.3   972.9  5081.3  976.31
  5141.3  975.79  5181.4  976.79  5381.4  975.87  5421.4  976.38  5441.4  975.79
  5451.4  974.86  5471.4  974.48  5491.4  976.26  5511.4  977.22  5581.4  978.94
#Mann= 3 ,-1 , 0
    4866     .05       0  5006.7     .05       0  5015.9     .05       0
Bank Sta=5006.7,5015.9
XS Rating Curve= 0 ,0
Exp/Cntr=0.3,0.1

Type RM Length L Ch R = 1 ,3238    ,420,420,420
BEGIN DESCRIPTION:
HARRIS BRANCH 3.0
END DESCRIPTION:
XS GIS Cut Line= 3
       2862955.7     10250853.11       2862771.5       10250816.
      2861955.65     10251103.12
#Sta/Elev= 30
  4812.1  978.26  4822.3  976.38  4832.4  977.11  4837.5  975.47  4852.9  976.47
  4883.2  974.05  4888.3  974.54  4903.9  972.65  4924.3  967.67  4934.1  966.64
    4990  964.78  5004.3  963.02  5004.8  962.52  5013.5  963.02  5034.6  965.45
  5048.6  971.52  5065.5  974.09  5228.8  973.64  5313.6  974.87  5431.8  973.95
  5451.4  971.22  5457.5  973.31  5462.8  972.52  5472.4  974.11  5483.1  975.71
  5488.4  974.69  5627.4  977.38  5733.7  979.18  5758.5  980.11  5864.9  983.87
#Mann= 7 ,-1 , 0
  4812.1     .05       0  5004.3     .05       0  5013.5     .05       0
  5472.4     .12       0  5627.4     .05       0  5733.7     .12       0
  5758.5     .05       0
Bank Sta=5004.3,5013.5
XS Rating Curve= 0 ,0
Exp/Cntr=0.3,0.1

Type RM Length L Ch R = 1 ,2818    ,524,524,524
BEGIN DESCRIPTION:
HARRIS BRANCH 2.0
END DESCRIPTION:
XS GIS Cut Line= 3
      2862755.64     10250403.12      2862643.25       10250431.
      2862055.67     10250803.12
#Sta/Elev= 30
  4884.2  977.34  4915.1  974.49  4935.7  973.64  4966.6   971.3  4990.2  960.47
  4991.6  960.47  4992.1  959.97  5000.3  959.97  5000.8  960.47  5014.1  962.21
  5050.5  963.54  5065.8  965.18    5080  970.32    5087  972.08  5102.2   972.7
  5138.7  972.98  5223.4  971.39  5296.3  972.44  5304.9  971.25  5311.6   969.2
  5363.3   968.7  5369.2  968.91  5384.5  971.71  5405.6  972.52  5435.1  973.23
  5442.1  972.55  5478.5  972.64  5593.8  974.41  5681.9  976.76  5695.5  977.67
#Mann= 3 ,-1 , 0
  4884.2     .05       0  4991.6     .03       0  5000.8     .05       0
Bank Sta=4991.6,5000.8
XS Rating Curve= 0 ,0
Exp/Cntr=0.3,0.1

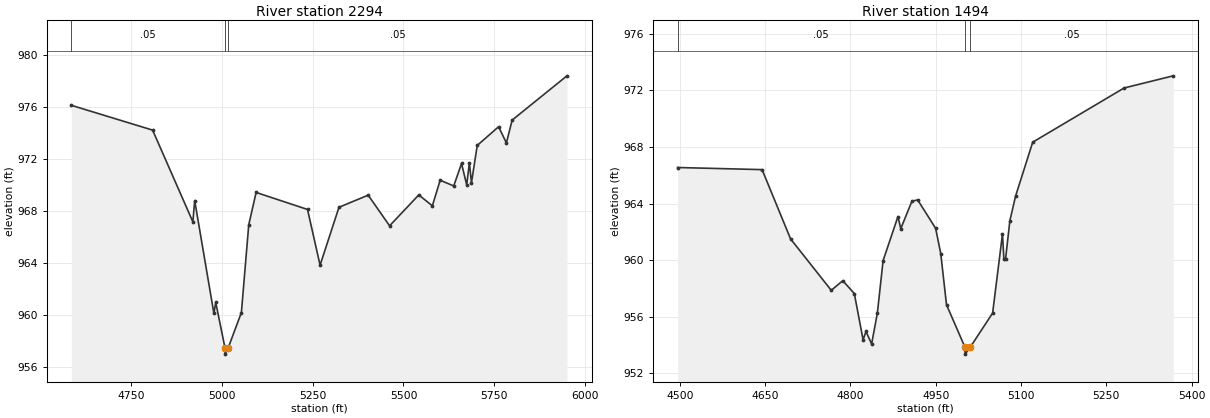
Type RM Length L Ch R = 1 ,2294    ,800,800,800
BEGIN DESCRIPTION:
Mapping XS a78f2e06
END DESCRIPTION:
XS GIS Cut Line= 3
      2862806.31     10250059.73      2862243.78     10249955.56
      2861556.28     10250351.39
#Sta/Elev= 30
  4584.9  976.13  4808.8  974.22  4919.7  967.16  4924.8  968.79  4977.7   960.1
  4982.7  960.96  5008.1  957.47  5008.6  956.97  5017.3  957.47  5053.4  960.17
  5073.7  966.93    5094  969.42  5235.6  968.11  5270.2  963.82  5322.3  968.28
  5402.7  969.21  5461.7  966.85  5542.1  969.23  5579.5  968.39    5601  970.36
  5638.4  969.92  5659.9  971.65  5674.1     970  5681.5   971.7  5687.3  970.17
  5703.1  973.04    5762  974.48  5783.5  973.23  5799.3  974.99  5950.3   978.4
#Mann= 3 ,-1 , 0
  4584.9     .05       0  5008.1     .03       0  5017.3     .05       0
Bank Sta=5008.1,5017.3
XS Rating Curve= 0 ,0
Exp/Cntr=0.3,0.1

Type RM Length L Ch R = 1 ,1494    ,0,0,0
BEGIN DESCRIPTION:
HARRIS BRANCH 1.0
END DESCRIPTION:
XS GIS Cut Line= 3
      2862832.35     10249340.98       2862265.7     10249247.97
      2861969.73     10249219.22
#Sta/Elev= 30
    4496  966.55  4644.6   966.4  4694.6  961.51  4766.2  957.87  4786.5  958.55
  4806.8  957.64  4822.2  954.37  4827.3  954.96  4837.2  954.08  4847.3  956.26
  4857.4  959.97  4883.5  963.08  4888.5  962.23  4908.1  964.17  4918.2  964.26
  4949.8  962.25  4958.8  960.46  4968.9  956.85  5001.2  953.86  5001.7  953.36
  5010.8  953.86    5050  956.26  5067.3  961.84  5069.8   960.1  5072.8   960.1
  5080.3  962.78  5090.3  964.52  5120.5  968.34  5281.2  972.17  5367.6  973.03
#Mann= 3 ,-1 , 0
    4496     .05       0  5001.2     .03       0  5010.8     .05       0
Bank Sta=5001.2,5010.8
XS Rating Curve= 0 ,0
Exp/Cntr=0.3,0.1

Chan Stop Cuts=-1
Use User Specified Reach Order=0
Composite Channel Slope=5