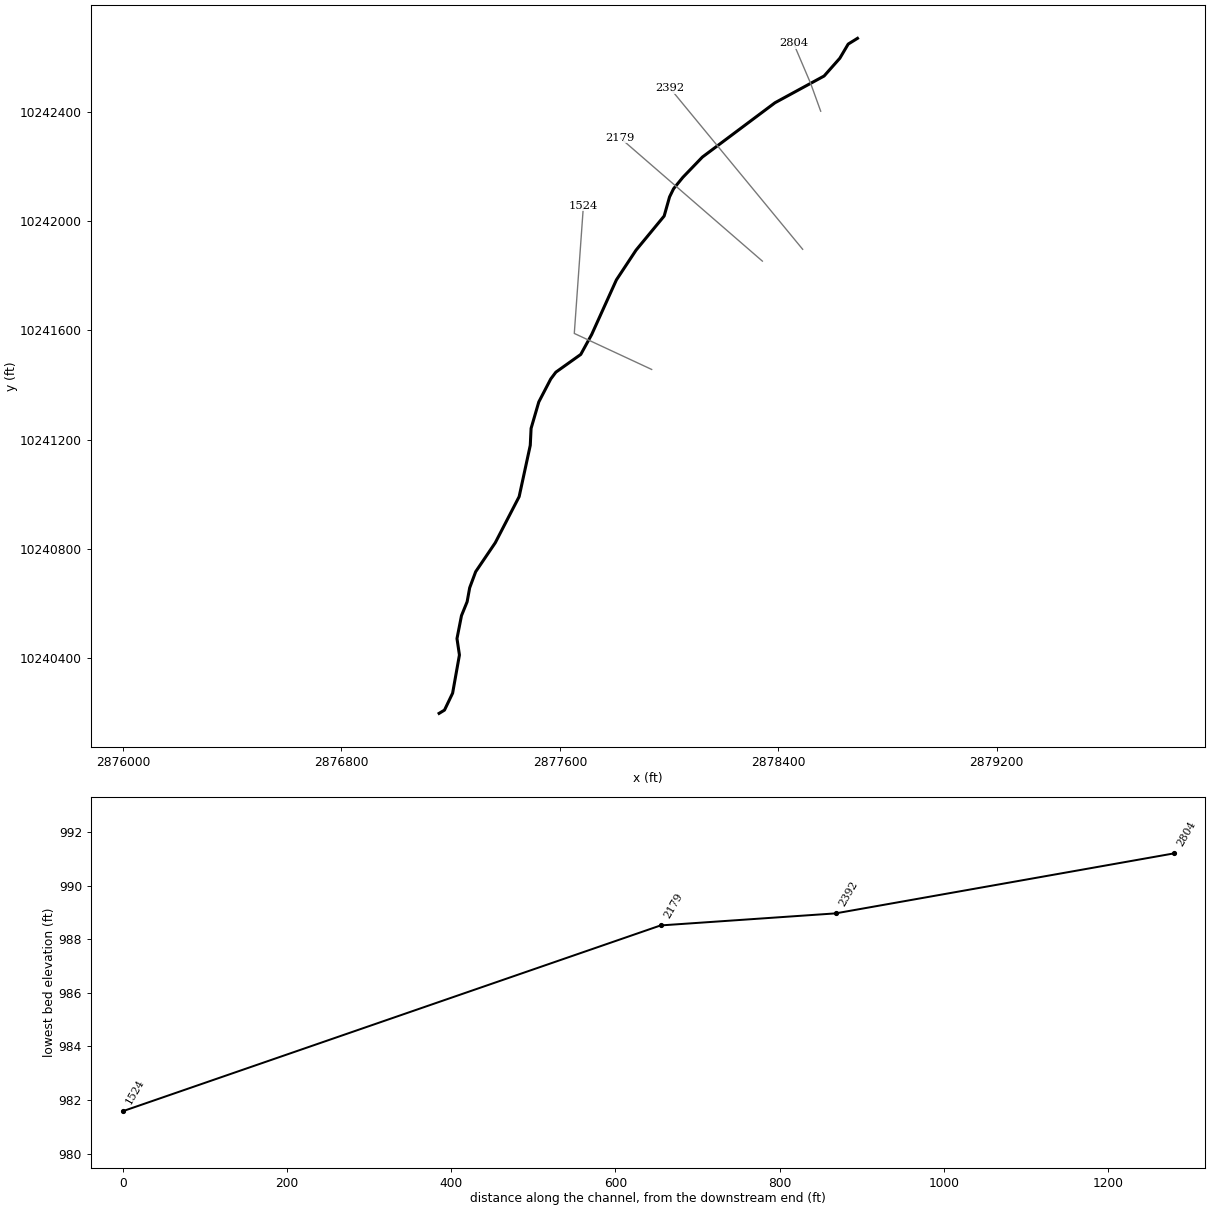
--- LITTLE LLANO 003.prj (project) ---

Proj Title=LITTLE LLANO 003 Base Level Engineering
Current Plan=p01
Default Exp/Contr=0.3,0.1
English Units
Geom File=g01
Flow File=f01
Plan File=p01
Y Axis Title=Elevation
X Axis Title(PF)=Main Channel Distance
X Axis Title(XS)=Station
BEGIN DESCRIPTION:
LITTLE LLANO 003
END DESCRIPTION:
DSS Export Rating Curves= 0
DSS Export Rating Curve Sorted= 0
DSS Export Volume Flow Curves= 0
DXF OffsetX= 0
DXF OffsetY= 0
DXF ScaleX= 1
DXF ScaleY= 10

--- LITTLE LLANO 003.p01 (plan) ---

Plan Title=Multiple Run
Short Identifier=Multiple
Geom File=g01
Flow File=f01
Subcritical Flow
K Sum by GR= 0
Std Step Tol= 0.01
Critical Tol= 0.01
Num of Std Step Trials= 20
Max Error Tol= 0.3
Flow Tol Ratio= 0.001
Split Flow NTrial= 30
Split Flow Tol= 0.02
Split Flow Ratio= 0.02
Log Output Level= 0
Friction Slope Method= 1
Unsteady Friction Slope Method= 2
Unsteady Bridges Friction Slope Method= 1
Parabolic Critical Depth
Global Vel Dist=  1 , 1 , 1
Global Log Level= 0
CheckData=True
Encroach Param= -1, 0, 0, 0
BEGIN DESCRIPTION:
Multiple Run
END DESCRIPTION:

--- LITTLE LLANO 003.f01 (steady flow) ---

Flow Title=Multiple
Number of Profiles=7
Profile Names=10-year,25-year,50-year,1pct_min,100-year,1pct_plu,500-year
River Rch & RM= LITTLE LLANO 003,Reach-1,2804
     488     791     965     724    1270    2227    1708
Boundary for River Rch & Prof#=LITTLE LLANO 003,Reach-1,1
Up Type=0
Dn Type=3
Dn Slope=0.005
Boundary for River Rch & Prof#=LITTLE LLANO 003,Reach-1,2
Up Type=0
Dn Type=3
Dn Slope=0.005
Boundary for River Rch & Prof#=LITTLE LLANO 003,Reach-1,3
Up Type=0
Dn Type=3
Dn Slope=0.005
Boundary for River Rch & Prof#=LITTLE LLANO 003,Reach-1,4
Up Type=0
Dn Type=3
Dn Slope=0.005
Boundary for River Rch & Prof#=LITTLE LLANO 003,Reach-1,5
Up Type=0
Dn Type=3
Dn Slope=0.005
Boundary for River Rch & Prof#=LITTLE LLANO 003,Reach-1,6
Up Type=0
Dn Type=3
Dn Slope=0.005
Boundary for River Rch & Prof#=LITTLE LLANO 003,Reach-1,7
Up Type=0
Dn Type=3
Dn Slope=0.005

--- LITTLE LLANO 003.g01 (geometry) ---

Geom Title=Existing Conditions
Program Version=4.10

River Reach=LITTLE LLANO 003,Reach-1
Reach XY= 30
       2878690.5       10242670.       2878656.5       10242649.
      2878625.75       10242597.      2878568.25       10242532.
      2878388.25       10242434.      2878122.25       10242235.
        2878051.       10242161.      2878016.75       10242119.
        2878002.       10242089.      2877982.25       10242019.
      2877879.25       10241894.      2877807.25       10241785.
      2877716.75       10241585.      2877676.75       10241512.
       2877585.5       10241447.      2877566.75       10241422.
        2877523.       10241338.      2877494.75       10241241.
      2877491.75       10241179.        2877451.       10240991.
       2877363.5       10240822.      2877291.75       10240716.
      2877269.75       10240657.       2877260.5       10240606.
      2877239.75       10240555.      2877223.25       10240471.
      2877232.25       10240411.      2877207.25       10240271.
       2877177.5       10240209.      2877157.75       10240197.

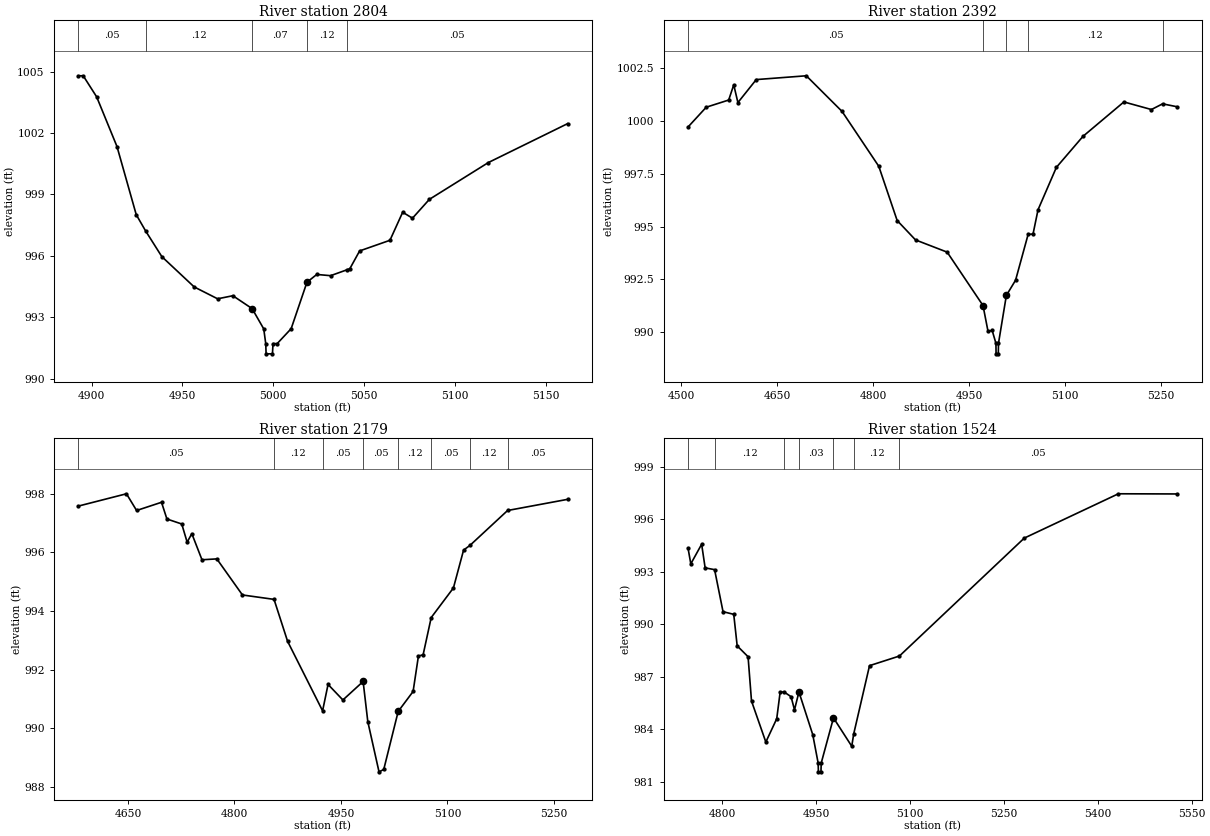
Type RM Length L Ch R = 1 ,2804    ,412,412,412
BEGIN DESCRIPTION:
LITTLE LLANO 003 2.0
END DESCRIPTION:
XS GIS Cut Line= 3
       2878555.7     10242403.08      2878519.25       10242504.
      2878455.68     10242653.12
#Sta/Elev= 30
  4892.7  1004.8  4895.4  1004.8  4902.8 1003.77    4914 1001.34  4924.6  998.01
  4929.8  997.21  4938.7  995.96  4956.5  994.48  4969.4   993.9  4977.8  994.05
  4988.4  993.42  4994.8  992.43  4995.9  991.71  4996.1  991.21  4999.6  991.21
  4999.9  991.71  5002.2  991.71  5009.9  992.44  5018.6  994.71    5024  995.09
  5031.6  995.03  5040.4  995.31  5042.2  995.37  5047.6  996.24  5064.3  996.76
  5071.3  998.13  5076.7  997.84    5086  998.76  5118.5 1000.56  5162.1 1002.46
#Mann= 5 ,-1 , 0
  4892.7     .05       0  4929.8     .12       0  4988.4     .07       0
  5018.6     .12       0  5040.4     .05       0
Bank Sta=4988.4,5018.6
XS Rating Curve= 0 ,0
Exp/Cntr=0.3,0.1

Type RM Length L Ch R = 1 ,2392    ,213,213,213
BEGIN DESCRIPTION:
Mapping XS f0186fd8
END DESCRIPTION:
XS GIS Cut Line= 2
      2878489.66      10241897.2      2878003.54     10242487.49
#Sta/Elev= 30
  4510.5  999.72    4539 1000.66  4574.1    1001    4582 1001.72  4588.5 1000.88
  4617.2 1001.97  4695.4 1002.15  4751.3 1000.46  4808.7  997.86  4837.4  995.29
  4866.1  994.37  4915.6  993.79  4971.6  991.26  4979.4  990.04  4985.9  990.08
  4991.8  989.47    4992  988.97  4995.5  988.97  4995.8  989.47  5008.1  991.74
  5022.5  992.46  5042.1  994.63  5049.8  994.65  5057.6   995.8  5086.3  997.81
  5127.9  999.28  5191.8 1000.91  5234.8 1000.55  5252.3 1000.82  5275.2 1000.68
#Mann= 5 ,-1 , 0
  4510.5     .05       0  4971.6     .05       0  5008.1     .05       0
  5042.1     .12       0  5252.3     .05       0
Bank Sta=4971.6,5008.1
XS Rating Curve= 0 ,0
Exp/Cntr=0.3,0.1

Type RM Length L Ch R = 1 ,2179    ,655,655,655
BEGIN DESCRIPTION:
Mapping XS b34ea36e
END DESCRIPTION:
XS GIS Cut Line= 2
      2878342.08     10241853.82      2877821.26      10242305.2
#Sta/Elev= 30
  4580.1  997.58  4647.9     998  4662.2  997.43  4697.3  997.71  4704.9  997.14
  4725.8  996.97  4733.4  996.35    4740  996.64  4754.3  995.75  4775.2  995.78
  4811.3  994.55  4855.8   994.4  4874.9  992.97  4924.2   990.6  4931.9   991.5
  4952.8  990.97  4981.3   991.6  4987.9  990.23 5003.69  988.52 5010.34   988.6
  5030.7  990.58  5051.7  991.26  5059.2  992.47  5065.8  992.51  5077.2  993.78
  5108.5  994.79  5122.8  996.08  5131.8  996.24  5184.8  997.43  5269.3  997.81
#Mann= 8 ,-1 , 0
  4580.1     .05       0  4855.8     .12       0  4924.2     .05       0
  4981.3     .05       0  5030.7     .12       0  5077.2     .05       0
  5131.8     .12       0  5184.8     .05       0
Bank Sta=4981.3,5030.7
XS Rating Curve= 0 ,0
Exp/Cntr=0.3,0.1

Type RM Length L Ch R = 1 ,1524    ,0,0,0
BEGIN DESCRIPTION:
LITTLE LLANO 003 1.0
END DESCRIPTION:
XS GIS Cut Line= 3
      2877936.45     10241457.01      2877653.03     10241588.89
      2877686.47       10242057.
#Sta/Elev= 30
  4745.1  994.36  4749.6  993.45  4766.9  994.57  4772.5  993.22  4787.6  993.12
  4801.1  990.72  4818.2  990.57  4823.7  988.77  4841.1  988.15  4846.6  985.62
  4869.5  983.28  4886.9  984.61  4892.4  986.14    4899  986.13  4909.8  985.87
  4915.3  985.12  4922.4  986.14  4944.5   983.7  4953.1  982.08  4953.5  981.58
  4957.6  981.58    4958  982.08  4977.6  984.66  5006.8  983.04  5009.9  983.74
  5035.2  987.64    5083  988.19  5282.5  994.92  5432.9  997.45    5527  997.44
#Mann= 7 ,-1 , 0
  4745.1     .05       0  4787.6     .12       0    4899     .05       0
  4922.4     .03       0  4977.6     .05       0  5009.9     .12       0
    5083     .05       0
Bank Sta=4922.4,4977.6
XS Rating Curve= 0 ,0
Exp/Cntr=0.3,0.1

Chan Stop Cuts=-1
Use User Specified Reach Order=0
Composite Channel Slope=5