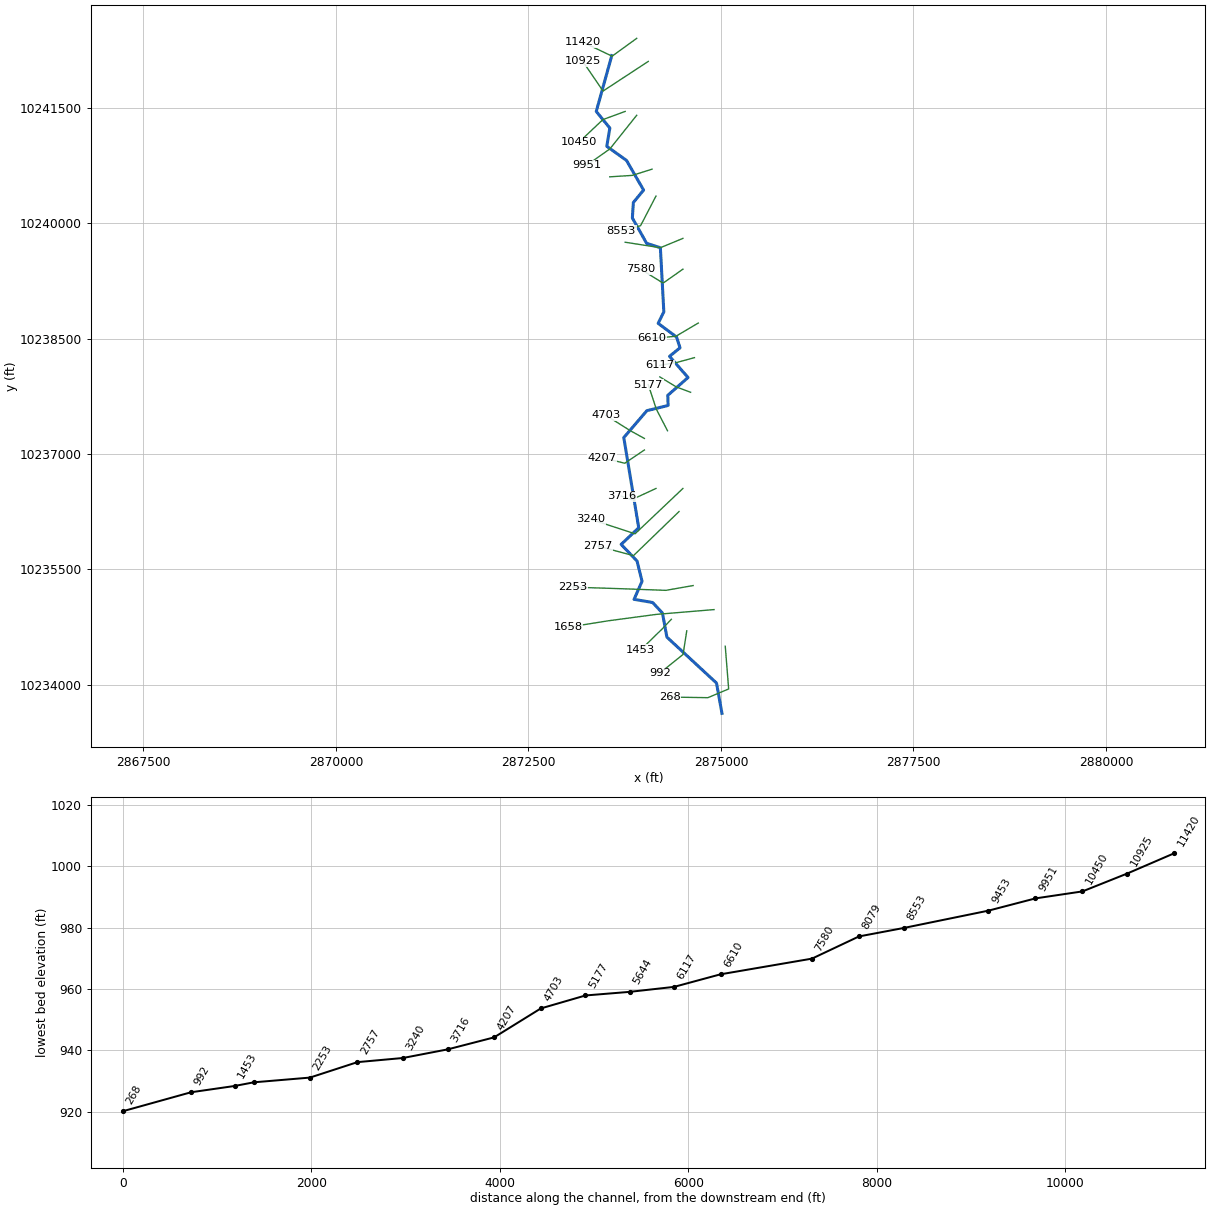
--- LITTLE LLANO 005.prj (project) ---

Proj Title=LITTLE LLANO 005 Base Level Engineering
Current Plan=p01
Default Exp/Contr=0.3,0.1
English Units
Geom File=g01
Flow File=f01
Plan File=p01
Y Axis Title=Elevation
X Axis Title(PF)=Main Channel Distance
X Axis Title(XS)=Station
BEGIN DESCRIPTION:
LITTLE LLANO 005
END DESCRIPTION:
DSS Export Rating Curves= 0
DSS Export Rating Curve Sorted= 0
DSS Export Volume Flow Curves= 0
DXF OffsetX= 0
DXF OffsetY= 0
DXF ScaleX= 1
DXF ScaleY= 10

--- LITTLE LLANO 005.p01 (plan) ---

Plan Title=Multiple Run
Short Identifier=Multiple
Geom File=g01
Flow File=f01
Subcritical Flow
K Sum by GR= 0
Std Step Tol= 0.01
Critical Tol= 0.01
Num of Std Step Trials= 20
Max Error Tol= 0.3
Flow Tol Ratio= 0.001
Split Flow NTrial= 30
Split Flow Tol= 0.02
Split Flow Ratio= 0.02
Log Output Level= 0
Friction Slope Method= 1
Unsteady Friction Slope Method= 2
Unsteady Bridges Friction Slope Method= 1
Parabolic Critical Depth
Global Vel Dist=  1 , 1 , 1
Global Log Level= 0
CheckData=True
Encroach Param= -1, 0, 0, 0
BEGIN DESCRIPTION:
Multiple Run
END DESCRIPTION:

--- LITTLE LLANO 005.f01 (steady flow) ---

Flow Title=Multiple
Number of Profiles=7
Profile Names=10-year,25-year,50-year,1pct_min,100-year,1pct_plu,500-year
River Rch & RM= LITTLE LLANO 005,Reach-1,11420
     465     758     807     565    1050    1950    1407
River Rch & RM= LITTLE LLANO 005,Reach-1,268
     467     762     812     569    1057    1962    1416
Boundary for River Rch & Prof#=LITTLE LLANO 005,Reach-1,1
Up Type=0
Dn Type=3
Dn Slope=0.005
Boundary for River Rch & Prof#=LITTLE LLANO 005,Reach-1,2
Up Type=0
Dn Type=3
Dn Slope=0.005
Boundary for River Rch & Prof#=LITTLE LLANO 005,Reach-1,3
Up Type=0
Dn Type=3
Dn Slope=0.005
Boundary for River Rch & Prof#=LITTLE LLANO 005,Reach-1,4
Up Type=0
Dn Type=3
Dn Slope=0.005
Boundary for River Rch & Prof#=LITTLE LLANO 005,Reach-1,5
Up Type=0
Dn Type=3
Dn Slope=0.005
Boundary for River Rch & Prof#=LITTLE LLANO 005,Reach-1,6
Up Type=0
Dn Type=3
Dn Slope=0.005
Boundary for River Rch & Prof#=LITTLE LLANO 005,Reach-1,7
Up Type=0
Dn Type=3
Dn Slope=0.005

--- LITTLE LLANO 005.g01 (geometry) ---

Geom Title=Existing Conditions
Program Version=4.10

River Reach=LITTLE LLANO 005,Reach-1
Reach XY= 30
        2873582.       10242179.      2873380.25       10241453.
      2873556.75       10241237.        2873517.       10241000.
       2873773.5       10240816.        2873995.       10240431.
      2873862.25       10240270.      2873849.25       10240068.
      2874034.75       10239739.        2874213.       10239682.
        2874258.       10238848.        2874184.       10238699.
        2874423.       10238521.        2874468.       10238381.
      2874331.75       10238270.      2874572.25       10237995.
      2874309.75       10237764.        2874313.       10237632.
        2874038.       10237564.        2873738.       10237214.
      2873931.75       10236042.       2873703.5       10235826.
       2873910.5       10235609.      2873974.75       10235346.
      2873871.25       10235112.      2874112.25       10235071.
        2874240.       10234934.      2874297.75       10234621.
        2874942.       10234024.        2875013.       10233630.

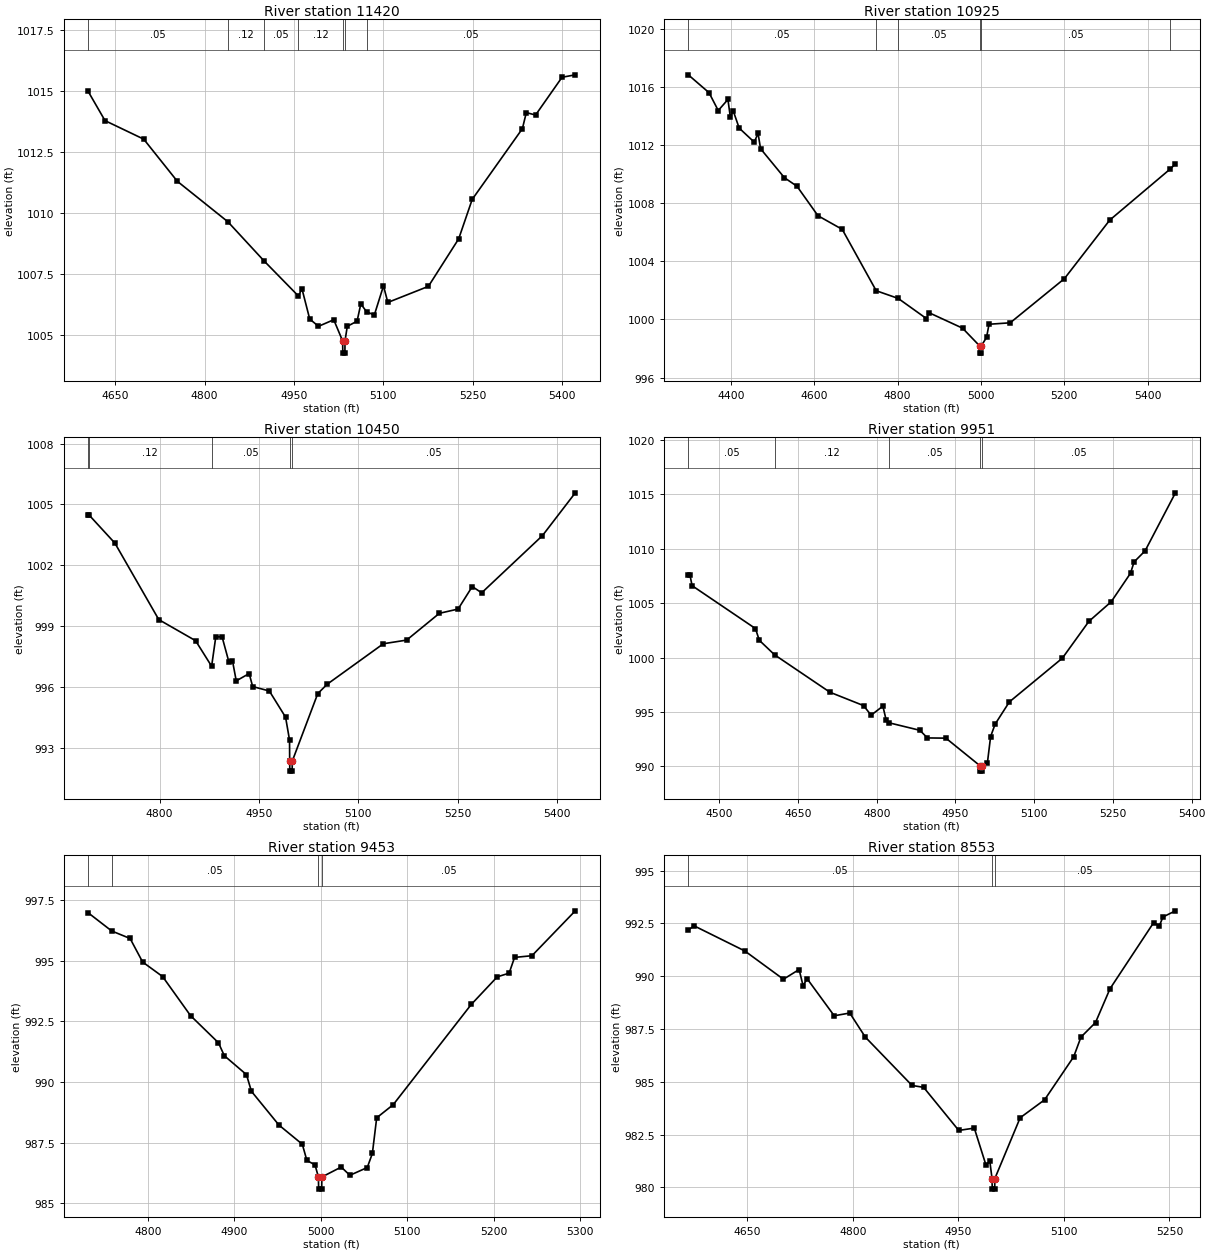
Type RM Length L Ch R = 1 ,11420   ,495,495,495
BEGIN DESCRIPTION:
LITTLE LLANO 005 22.0
END DESCRIPTION:
XS GIS Cut Line= 3
      2873905.72     10242403.13        2873586.       10242171.
      2873205.66     10242353.13
#Sta/Elev= 30
  4604.9 1014.98  4633.2 1013.78  4698.1 1013.02  4754.5 1011.29  4839.2 1009.63
  4899.6 1008.03  4957.6 1006.58  4963.3 1006.89  4976.4 1005.64  4991.1 1005.34
  5016.7 1005.61  5031.6 1004.74  5031.9 1004.24  5035.4 1004.24  5035.6 1004.74
  5039.4 1005.34  5055.8 1005.55  5062.1 1006.26  5071.7 1005.94  5084.7  1005.8
  5100.1    1007  5107.4 1006.32  5175.4 1006.98  5226.2 1008.93  5248.9 1010.55
    5333 1013.45  5339.6 1014.11  5355.1 1014.01  5399.5 1015.56  5421.7 1015.66
#Mann= 7 ,-1 , 0
  4604.9     .05       0  4839.2     .12       0  4899.6     .05       0
  4957.6     .12       0  5031.6     .07       0  5035.6     .12       0
  5071.7     .05       0
Bank Sta=5031.6,5035.6
XS Rating Curve= 0 ,0
Exp/Cntr=0.3,0.1

Type RM Length L Ch R = 1 ,10925   ,475,475,475
BEGIN DESCRIPTION:
LITTLE LLANO 005 21.0
END DESCRIPTION:
XS GIS Cut Line= 3
      2874055.68     10242103.11      2873468.75       10241718.
      2873205.68     10242103.12
#Sta/Elev= 30
    4298 1016.86  4347.7 1015.63  4369.8  1014.4    4393 1015.16    4399 1013.92
  4405.6 1014.39    4420 1013.19  4456.2 1012.22  4465.3 1012.83  4471.3 1011.77
  4528.5 1009.77  4558.7 1009.18    4609 1007.15  4667.2 1006.21  4748.7 1001.98
  4801.5 1001.45  4869.2 1000.06  4875.1 1000.47  4955.8   999.4  4996.7  998.18
    4997  997.68  5000.5  997.68  5000.7  998.18  5013.3  998.76  5019.3  999.67
  5070.1  999.77    5200 1002.81  5308.9 1006.85  5453.9 1010.37  5466.4 1010.72
#Mann= 6 ,-1 , 0
    4298     .05       0  4748.7     .12       0  4801.5     .05       0
  4996.7     .05       0  5000.7     .05       0  5453.9     .12       0
Bank Sta=4996.7,5000.7
XS Rating Curve= 0 ,0
Exp/Cntr=0.3,0.1

Type RM Length L Ch R = 1 ,10450   ,499,499,499
BEGIN DESCRIPTION:
LITTLE LLANO 005 20.0
END DESCRIPTION:
XS GIS Cut Line= 3
      2873755.65      10241453.1       2873466.5       10241347.
      2873155.65     10241053.08
#Sta/Elev= 30
    4692  1004.5  4692.7  1004.5  4732.4 1003.09  4798.7  999.32  4854.3  998.28
  4878.5  997.02  4884.8  998.47  4894.3  998.47  4904.7  997.22    4910  997.29
  4915.7   996.3  4935.2  996.66  4940.5  996.02  4965.7   995.8  4990.2  994.51
  4996.2  993.38  4996.4  992.35  4996.6  991.85  5000.1  991.85  5000.4  992.35
  5038.8  995.67  5052.9  996.13  5137.9  998.13  5173.1  998.31  5222.5  999.63
  5250.8  999.84  5272.2 1000.95  5286.4 1000.64  5378.2 1003.46  5427.8 1005.57
#Mann= 5 ,-1 , 0
    4692     .05       0  4692.7     .12       0  4878.5     .05       0
  4996.4     .05       0  5000.4     .05       0
Bank Sta=4996.4,5000.4
XS Rating Curve= 0 ,0
Exp/Cntr=0.3,0.1

Type RM Length L Ch R = 1 ,9951    ,498,498,498
BEGIN DESCRIPTION:
LITTLE LLANO 005 19.0
END DESCRIPTION:
XS GIS Cut Line= 3
      2873905.69     10241403.12      2873557.25       10240966.
      2873255.72     10240753.13
#Sta/Elev= 30
    4441 1007.58  4444.2 1007.58  4448.2 1006.61  4568.9 1002.67  4576.3 1001.59
  4605.3 1000.26  4710.8  996.82  4774.9  995.59  4789.3  994.71  4811.7  995.54
  4818.1  994.24  4823.5  994.01  4882.2  993.32  4896.6  992.62  4931.8   992.6
  4996.6  990.07  4996.9  989.57  5000.4  989.57  5000.6  990.07  5010.9  990.35
    5017  992.75  5025.6  993.89  5052.7  995.93  5153.7  999.95  5204.2 1003.33
  5246.7 1005.13  5283.5 1007.75  5290.3 1008.79  5311.3 1009.81  5369.1 1015.14
#Mann= 5 ,-1 , 0
    4441     .05       0  4605.3     .12       0  4823.5     .05       0
  4996.6     .03       0  5000.6     .05       0
Bank Sta=4996.6,5000.6
XS Rating Curve= 0 ,0
Exp/Cntr=0.3,0.1

Type RM Length L Ch R = 1 ,9453    ,900,900,900
BEGIN DESCRIPTION:
LITTLE LLANO 005 18.0
END DESCRIPTION:
XS GIS Cut Line= 3
      2874105.73     10240703.12      2873849.25       10240622.
      2873555.66     10240603.11
#Sta/Elev= 30
    4731  996.97  4758.2  996.22  4779.5  995.91    4794  994.94  4817.1  994.34
  4849.4  992.73  4881.7  991.61  4888.4  991.08    4914   990.3  4919.8  989.61
  4951.6  988.22  4978.6  987.43  4983.9  986.76  4993.3  986.58  4997.2  986.08
  4997.5  985.58    5001  985.58  5001.2  986.08  5023.6  986.49  5033.6  986.15
  5053.7  986.47  5059.6  987.05  5064.6  988.52  5083.7  989.06  5173.9  993.19
    5204  994.33  5217.7  994.48    5224  995.13  5244.1   995.2  5294.2  997.05
#Mann= 4 ,-1 , 0
    4731     .12       0  4758.2     .05       0  4997.2     .05       0
  5001.2     .05       0
Bank Sta=4997.2,5001.2
XS Rating Curve= 0 ,0
Exp/Cntr=0.3,0.1

Type RM Length L Ch R = 1 ,8553    ,474,474,474
BEGIN DESCRIPTION:
LITTLE LLANO 005 17.0
END DESCRIPTION:
XS GIS Cut Line= 3
      2874155.68     10240353.11        2873956.       10239968.
      2873705.67     10239903.11
#Sta/Elev= 30
  4566.2  992.19  4574.4  992.39  4646.5   991.2  4701.4  989.86  4723.7  990.32
  4729.3  989.56  4735.2  989.88  4773.6  988.13  4795.7  988.26  4817.8  987.12
  4884.2  984.83  4900.7  984.74  4950.6   982.7  4972.7  982.81  4989.2  981.07
  4994.8  981.24  4997.9  980.42  4998.2  979.92  5001.7  979.92  5001.9  980.42
  5037.9   983.3  5072.6  984.15    5114  986.19  5124.3  987.12    5145  987.81
  5165.6  989.41  5227.6  992.54  5235.7  992.39  5240.9  992.81  5258.6   993.1
#Mann= 3 ,-1 , 0
  4566.2     .05       0  4997.9     .05       0  5001.9     .05       0
Bank Sta=4997.9,5001.9
XS Rating Curve= 0 ,0
Exp/Cntr=0.3,0.1

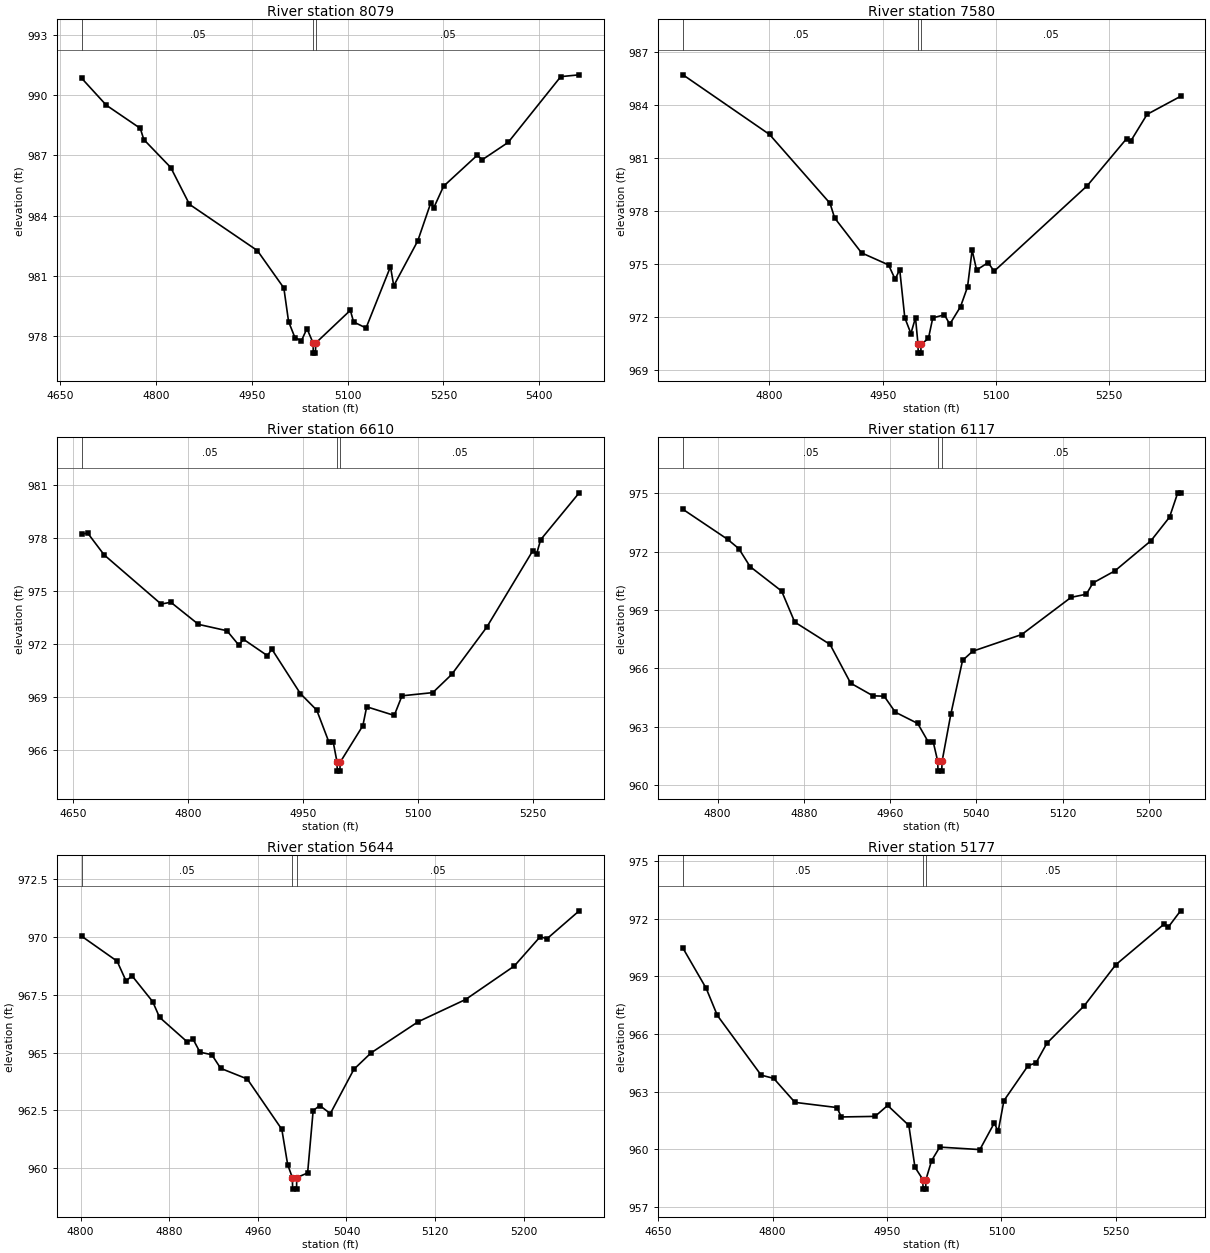
Type RM Length L Ch R = 1 ,8079    ,499,499,499
BEGIN DESCRIPTION:
LITTLE LLANO 005 16.0
END DESCRIPTION:
XS GIS Cut Line= 3
      2874505.73     10239803.13        2874213.       10239682.
       2873755.7     10239753.11
#Sta/Elev= 30
  4683.2  990.84  4721.8   989.5    4775  988.35  4780.6  987.79  4822.8   986.4
  4852.1  984.57  4958.5  982.27    5000  980.41  5007.4  978.74  5017.5  977.93
  5027.6  977.79  5036.2  978.39  5045.9  977.67  5046.1  977.17  5049.6  977.17
  5049.9  977.67  5104.2   979.3  5109.3  978.72  5128.8  978.42  5167.1  981.47
  5172.2  980.52  5209.8  982.75    5230  984.62  5235.1  984.41  5250.3  985.47
    5303  987.01    5311  986.79  5351.5  987.65  5433.9  990.92  5462.8  991.01
#Mann= 3 ,-1 , 0
  4683.2     .05       0  5045.9     .03       0  5049.9     .05       0
Bank Sta=5045.9,5049.9
XS Rating Curve= 0 ,0
Exp/Cntr=0.3,0.1

Type RM Length L Ch R = 1 ,7580    ,970,970,970
BEGIN DESCRIPTION:
LITTLE LLANO 005 15.0
END DESCRIPTION:
XS GIS Cut Line= 3
      2874505.72     10239403.14      2874248.75       10239222.
      2873955.69      10239403.1
#Sta/Elev= 30
  4685.6   985.7  4800.2  982.32  4880.3  978.42  4886.4  977.59  4922.1  975.61
  4957.8  974.93  4966.5  974.12  4972.6  974.66  4979.3  971.94  4987.4  971.04
  4993.5  971.94  4996.8  970.43  4997.1  969.93  5000.6  969.93  5000.8  970.43
  5010.6  970.76  5016.4  971.93  5031.8   972.1  5038.9  971.57  5053.1  972.56
  5062.4  973.68  5068.5  975.77  5074.4  974.64  5089.7  975.06  5097.6  974.57
    5221  979.42    5273  982.08  5278.9  981.97  5300.2  983.46  5344.5  984.48
#Mann= 3 ,-1 , 0
  4685.6     .05       0  4996.8     .03       0  5000.8     .05       0
Bank Sta=4996.8,5000.8
XS Rating Curve= 0 ,0
Exp/Cntr=0.3,0.1

Type RM Length L Ch R = 1 ,6610    ,493,493,493
BEGIN DESCRIPTION:
LITTLE LLANO 005 14.0
END DESCRIPTION:
XS GIS Cut Line= 3
      2874705.72     10238703.13      2874414.25       10238531.
      2874105.71     10238503.11
#Sta/Elev= 30
  4661.5  978.23  4669.4  978.28  4690.8  977.05    4765  974.27  4777.7  974.37
  4813.7  973.12  4850.8  972.76  4866.4  971.94  4872.2  972.28  4903.5  971.35
  4909.3  971.72  4946.4  969.21  4967.8  968.27  4983.5  966.48  4989.3  966.46
  4994.3  965.32  4994.5  964.82    4998  964.82  4998.3  965.32  5027.9  967.39
  5032.9  968.46  5068.8  967.97  5078.9  969.08    5119  969.26  5143.7  970.29
  5189.3  972.96  5249.4  977.29  5254.4  977.12  5259.6  977.91  5309.8  980.56
#Mann= 3 ,-1 , 0
  4661.5     .05       0  4994.3     .05       0  4998.3     .05       0
Bank Sta=4994.3,4998.3
XS Rating Curve= 0 ,0
Exp/Cntr=0.3,0.1

Type RM Length L Ch R = 1 ,6117    ,473,473,473
BEGIN DESCRIPTION:
LITTLE LLANO 005 13.0
END DESCRIPTION:
XS GIS Cut Line= 3
      2874655.66     10238253.11      2874431.75       10238192.
      2874205.67     10238153.11
#Sta/Elev= 30
  4767.9  974.17  4809.3  972.63  4819.7  972.15  4830.1  971.23  4859.4  969.97
  4871.5  968.38  4904.3  967.23  4923.4  965.24  4944.1  964.59  4954.5  964.57
  4964.8  963.75  4985.6  963.17  4995.4  962.22    5000  962.22  5004.2  961.22
  5004.4  960.72  5007.9  960.72  5008.2  961.22  5016.3  963.64  5027.2  966.41
  5036.6  966.88  5082.1  967.74  5127.9  969.65    5142  969.81  5148.2  970.39
  5168.5  971.01    5202  972.56  5219.2  973.77  5226.8  975.02  5229.4  975.02
#Mann= 3 ,-1 , 0
  4767.9     .05       0  5004.2     .05       0  5008.2     .05       0
Bank Sta=5004.2,5008.2
XS Rating Curve= 0 ,0
Exp/Cntr=0.3,0.1

Type RM Length L Ch R = 1 ,5644    ,467,467,467
BEGIN DESCRIPTION:
LITTLE LLANO 005 12.0
END DESCRIPTION:
XS GIS Cut Line= 3
      2874605.68     10237803.11      2874419.25       10237873.
      2874205.67     10238003.12
#Sta/Elev= 30
  4800.9  970.04  4832.9  968.96    4841   968.1  4846.3  968.33    4865  967.21
  4871.2  966.53  4896.1  965.47  4901.5  965.58  4907.7  965.02  4918.4  964.91
  4926.4  964.32  4950.4  963.86  4981.6  961.68  4986.9  960.15  4991.1  959.59
  4991.4  959.09  4994.9  959.09  4995.1  959.59  5004.9  959.79  5009.9  962.49
  5015.9  962.71  5025.4  962.36  5046.7  964.28  5062.2  964.99  5104.8  966.34
  5147.5   967.3  5191.5  968.75  5214.9  970.02    5221  969.93  5250.1  971.14
#Mann= 3 ,-1 , 0
  4800.9     .05       0  4991.1     .03       0  4995.1     .05       0
Bank Sta=4991.1,4995.1
XS Rating Curve= 0 ,0
Exp/Cntr=0.3,0.1

Type RM Length L Ch R = 1 ,5177    ,474,474,474
BEGIN DESCRIPTION:
LITTLE LLANO 005 11.0
END DESCRIPTION:
XS GIS Cut Line= 3
      2874305.67     10237303.13      2874159.75       10237585.
      2874055.68     10237903.11
#Sta/Elev= 30
  4682.6  970.47    4713  968.38  4727.6  966.97    4785  963.86  4801.5  963.69
  4829.3  962.44  4884.4  962.17  4890.1  961.68  4934.3  961.71  4950.8  962.28
  4978.6  961.24  4986.6  959.06    4997  958.42  4997.2  957.92  5000.7  957.92
    5001  958.42  5008.5  959.41  5019.1  960.11  5071.7  959.98  5090.5  961.36
  5095.7  960.93  5103.2  962.53  5134.8  964.35  5145.3   964.5  5159.5  965.52
  5208.4  967.47  5249.8  969.61  5313.5  971.74  5318.8  971.58  5334.7  972.42
#Mann= 3 ,-1 , 0
  4682.6     .05       0    4997     .03       0    5001     .05       0
Bank Sta=4997,5001
XS Rating Curve= 0 ,0
Exp/Cntr=0.3,0.1

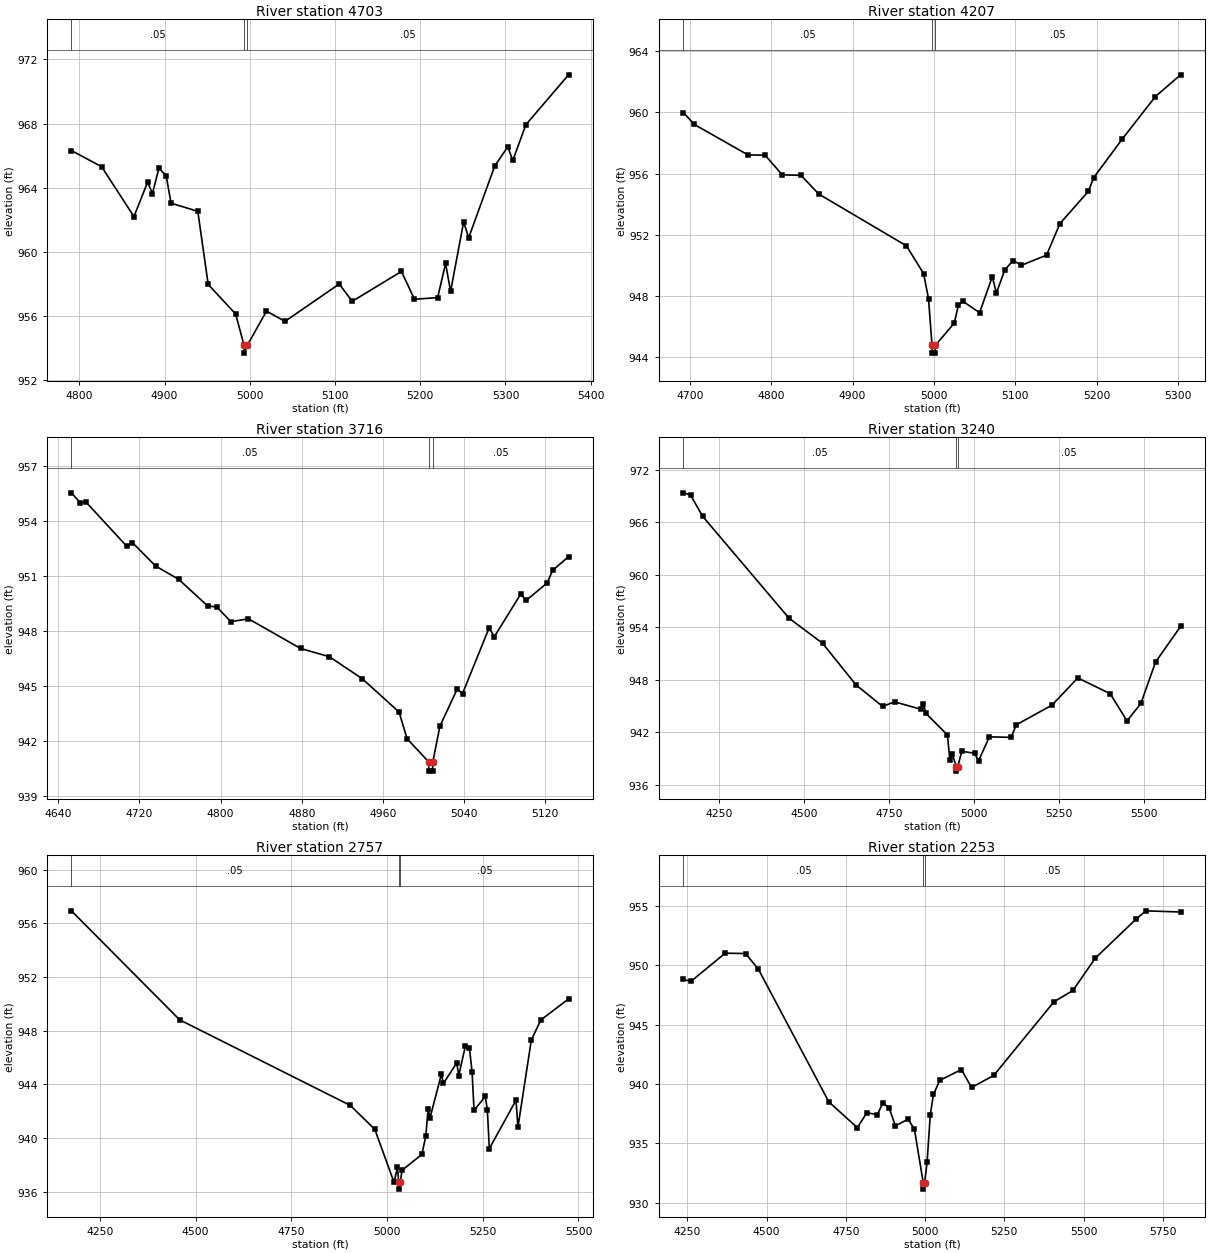
Type RM Length L Ch R = 1 ,4703    ,496,496,496
BEGIN DESCRIPTION:
LITTLE LLANO 005 10.0
END DESCRIPTION:
XS GIS Cut Line= 3
      2874005.64     10237203.13      2873822.25       10237304.
      2873505.67     10237503.12
#Sta/Elev= 30
  4790.7  966.32  4826.2  965.31  4864.1   962.2  4880.1  964.35  4885.8  963.64
  4893.4  965.22  4901.9  964.75  4907.6  963.04    4939  962.53  4951.2  957.97
  4983.4  956.13  4993.2  954.19  4993.4  953.69  4997.2  954.19  5019.6  956.31
  5041.3  955.67  5104.9     958  5120.2  956.92  5177.9  958.78  5193.2  957.05
  5220.4  957.15  5229.7  959.28  5235.6  957.54  5250.9  961.87  5256.8  960.88
  5287.4  965.36  5302.7  966.55  5308.6   965.7  5323.9  967.93    5374  971.04
#Mann= 3 ,-1 , 0
  4790.7     .05       0  4993.2     .03       0  4997.2     .05       0
Bank Sta=4993.2,4997.2
XS Rating Curve= 0 ,0
Exp/Cntr=0.3,0.1

Type RM Length L Ch R = 1 ,4207    ,491,491,491
BEGIN DESCRIPTION:
LITTLE LLANO 005 9.0
END DESCRIPTION:
XS GIS Cut Line= 3
      2874005.68     10237053.11      2873750.25       10236881.
      2873455.65     10236953.12
#Sta/Elev= 30
    4692  959.99  4705.5  959.21  4771.4  957.22  4792.5   957.2  4813.5  955.92
  4836.7  955.88  4858.4  954.66  4966.3  951.27  4987.3  949.46  4993.4  947.82
  4997.7  944.75    4998  944.25  5001.5  944.25  5001.7  944.75    5025  946.21
  5030.2  947.39  5035.6  947.64  5056.2   946.9  5071.8  949.25  5076.9  948.18
  5087.1  949.69  5097.4  950.31  5107.7     950  5138.5  950.66    5155  952.73
    5190  954.84  5196.6  955.74  5231.2  958.23  5272.4  961.04  5303.3  962.46
#Mann= 3 ,-1 , 0
    4692     .05       0  4997.7     .05       0  5001.7     .05       0
Bank Sta=4997.7,5001.7
XS Rating Curve= 0 ,0
Exp/Cntr=0.3,0.1

Type RM Length L Ch R = 1 ,3716    ,476,476,476
BEGIN DESCRIPTION:
LITTLE LLANO 005 8.0
END DESCRIPTION:
XS GIS Cut Line= 3
      2874155.73     10236553.13        2873841.       10236407.
      2873705.64     10236453.13
#Sta/Elev= 30
    4653  955.53  4661.7  954.99  4667.3  955.03  4707.5  952.62  4713.1  952.82
  4735.9  951.54  4758.8  950.81  4787.3  949.36  4796.4   949.3  4810.2   948.5
  4827.5  948.66  4878.9  947.04  4907.3  946.59  4939.7  945.39    4976  943.57
  4983.8  942.12  5005.2  940.85  5005.4  940.35  5008.9  940.35  5009.2  940.85
  5016.2   942.8  5033.2  944.82  5038.5  944.58  5064.6  948.15  5069.9  947.69
  5095.9  950.01  5101.2  949.66  5121.8  950.61  5127.3   951.3    5143  952.05
#Mann= 3 ,-1 , 0
    4653     .05       0  5005.2     .05       0  5009.2     .05       0
Bank Sta=5005.2,5009.2
XS Rating Curve= 0 ,0
Exp/Cntr=0.3,0.1

Type RM Length L Ch R = 1 ,3240    ,483,483,483
BEGIN DESCRIPTION:
LITTLE LLANO 005 7.0
END DESCRIPTION:
XS GIS Cut Line= 3
      2874505.66     10236553.09      2873884.75       10235964.
      2873305.65     10236153.12
#Sta/Elev= 30
  4144.1  969.35  4165.3  969.09  4200.5  966.68  4455.3  955.02  4554.4  952.14
  4653.5  947.36  4731.2  944.93  4766.4  945.45  4844.5   944.6  4851.4  945.24
  4858.6  944.14  4922.1  941.67  4929.4  938.83  4936.3  939.48  4948.5  938.03
  4948.7  937.53  4952.5  938.03  4964.6   939.8  5002.1  939.57    5014  938.72
  5045.9  941.45  5109.7  941.39  5125.3  942.83  5230.5  945.08  5306.3  948.19
  5401.9  946.38  5451.4  943.27  5492.3  945.27  5535.5     950  5609.2  954.07
#Mann= 3 ,-1 , 0
  4144.1     .05       0  4948.5     .03       0  4952.5     .05       0
Bank Sta=4948.5,4952.5
XS Rating Curve= 0 ,0
Exp/Cntr=0.3,0.1

Type RM Length L Ch R = 1 ,2757    ,504,504,504
BEGIN DESCRIPTION:
LITTLE LLANO 005 6.0
END DESCRIPTION:
XS GIS Cut Line= 3
      2874455.68     10236253.11       2873863.5       10235680.
      2873405.66     10235803.12
#Sta/Elev= 30
  4175.9  956.93  4458.7   948.8  4904.3  942.42  4968.1  940.64  5018.4  936.69
  5027.4  937.81  5030.6  936.68  5030.9  936.18  5034.6  936.68  5039.2  937.58
  5090.9  938.77  5101.3  940.11  5107.4  942.18  5112.5  941.52  5142.1  944.75
  5147.3  944.06  5182.1  945.59  5187.3  944.65  5204.8  946.86  5215.2  946.71
  5222.1  944.95  5227.3  942.05  5256.6  943.09    5262  942.11  5267.2   939.2
  5336.8   942.8    5342  940.81  5376.8  947.29  5401.6  948.79  5474.1  950.36
#Mann= 3 ,-1 , 0
  4175.9     .05       0  5030.6     .05       0  5034.6     .05       0
Bank Sta=5030.6,5034.6
XS Rating Curve= 0 ,0
Exp/Cntr=0.3,0.1

Type RM Length L Ch R = 1 ,2253    ,595,595,595
BEGIN DESCRIPTION:
Mapping XS e980c260
END DESCRIPTION:
XS GIS Cut Line= 4
      2874638.92     10235291.33      2874284.77     10235228.83
      2873722.27     10235249.67      2873076.42      10235270.5
#Sta/Elev= 30
  4237.5  948.82  4261.1  948.65  4369.4  951.03  4433.7     951  4474.3  949.67
  4696.3   938.5  4786.3  936.32  4816.4  937.58  4849.6  937.42  4866.4  938.39
  4886.4  938.01  4906.4  936.47  4946.4  937.04  4966.5  936.19  4994.5  931.64
  4994.7  931.14  4998.5  931.64  5006.5  933.44  5016.5  937.41  5026.5  939.12
  5046.5  940.31  5114.8  941.22  5146.6  939.71  5216.6  940.72  5406.7  946.93
  5466.8  947.89  5536.8   950.6  5666.9  953.93  5696.9   954.6  5806.2   954.5
#Mann= 3 ,-1 , 0
  4237.5     .05       0  4994.5     .03       0  4998.5     .05       0
Bank Sta=4994.5,4998.5
XS Rating Curve= 0 ,0
Exp/Cntr=0.3,0.1

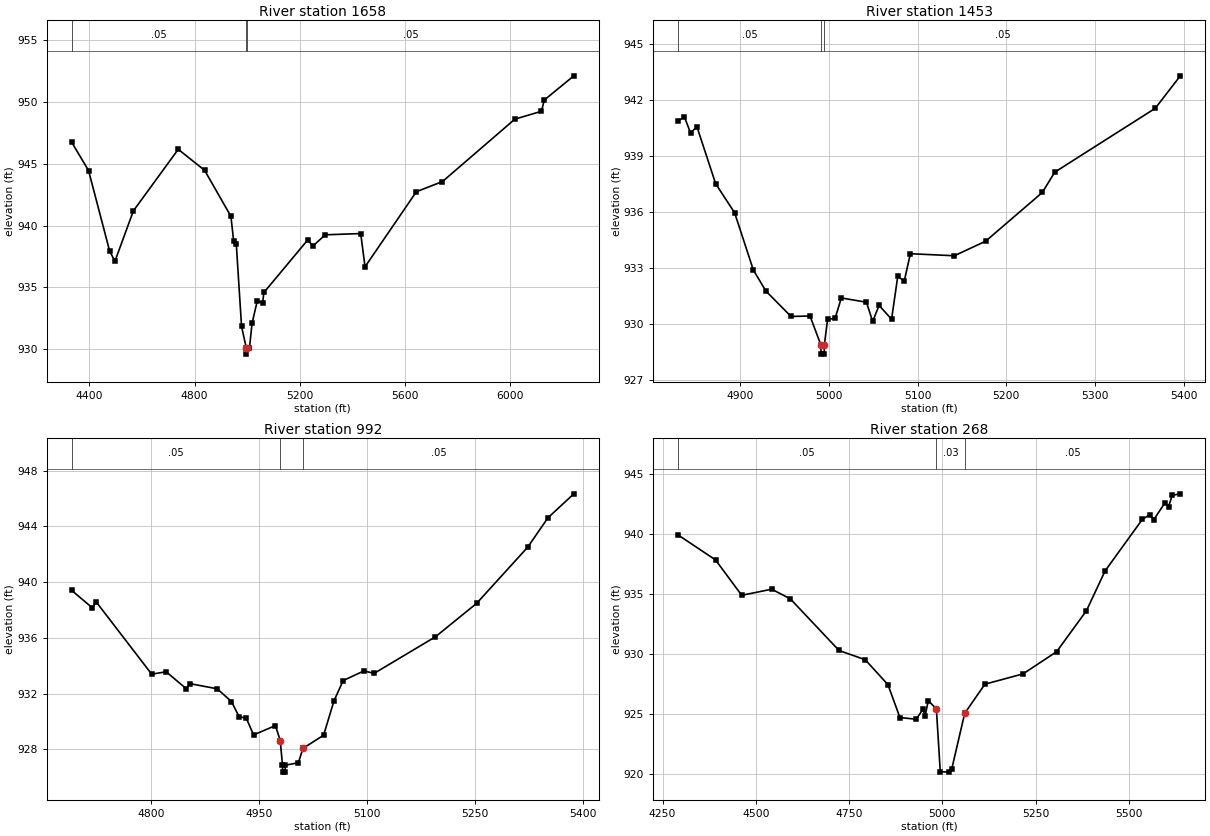
Type RM Length L Ch R = 1 ,1658    ,205,205,205
BEGIN DESCRIPTION:
Mapping XS 064beda6
END DESCRIPTION:
XS GIS Cut Line= 4
      2874909.81     10234978.84      2874159.77     10234916.33
      2873534.77       10234833.      2873013.96     10234749.67
#Sta/Elev= 30
  4332.2  946.76  4396.5  944.46  4476.8  937.94  4496.9  937.12  4567.1   941.2
  4737.7  946.18  4838.1  944.48  4938.2  940.75  4948.5  938.76  4958.5  938.54
  4978.6  931.84  4996.6   930.1  4996.9   929.6  5000.6   930.1  5008.7  930.11
  5018.7  932.11  5038.8  933.94  5058.6  933.73  5063.6  934.59  5230.2  938.84
  5250.4  938.36  5297.1  939.26    5432  939.36  5448.4  936.67  5643.8  942.75
    5743  943.57  6018.3  948.62  6119.5  949.26  6130.4  950.17  6242.8  952.13
#Mann= 3 ,-1 , 0
  4332.2     .05       0  4996.6     .03       0  5000.6     .05       0
Bank Sta=4996.6,5000.6
XS Rating Curve= 0 ,0
Exp/Cntr=0.3,0.1

Type RM Length L Ch R = 1 ,1453    ,461,461,461
BEGIN DESCRIPTION:
LITTLE LLANO 005 3.0
END DESCRIPTION:
XS GIS Cut Line= 3
      2874355.69     10234853.12      2874238.75       10234730.
      2873955.66     10234453.09
#Sta/Elev= 30
  4830.2   940.9  4837.3  941.11  4844.2  940.25  4851.4  940.58  4872.5  937.53
  4893.9  935.97    4915   932.9  4929.1  931.78  4957.4  930.42  4978.8  930.44
    4991   928.9  4991.3   928.4  4994.8   928.4    4995   928.9  4998.6  930.27
    5007  930.31  5014.1  931.41  5042.4  931.18  5049.4  930.15  5056.6  931.01
  5070.7  930.27  5077.7  932.58  5084.9   932.3  5091.9  933.78  5141.4  933.67
  5176.7  934.45  5240.5  937.06  5254.6  938.15  5367.8  941.57    5396  943.31
#Mann= 3 ,-1 , 0
  4830.2     .05       0    4991     .03       0    4995     .05       0
Bank Sta=4991,4995
XS Rating Curve= 0 ,0
Exp/Cntr=0.3,0.1

Type RM Length L Ch R = 1 ,992     ,724,724,724
BEGIN DESCRIPTION:
LITTLE LLANO 005 2.0
END DESCRIPTION:
XS GIS Cut Line= 3
      2874555.68     10234703.08      2874507.75       10234396.
      2874205.69     10234153.12
#Sta/Elev= 30
  4689.2   939.4    4718  938.15  4723.1  938.59  4800.5  933.39  4820.7  933.56
  4848.7  932.34  4853.7  932.71  4891.6  932.34  4911.5  931.42    4922  930.34
  4932.1  930.23  4942.2  929.03  4972.6   929.7  4979.3  928.62  4982.4  926.86
  4982.6  926.36  4986.1  926.36  4986.4  926.86  5004.5  927.03  5010.8  928.06
  5039.6  929.01    5054  931.47  5066.8  932.93  5095.6  933.62    5110  933.45
  5195.1  936.07  5252.4  938.47  5323.4   942.5  5351.6  944.61  5387.6  946.33
#Mann= 3 , 0 , 0
  4689.2     .05       0  4979.3     .03       0  5010.8     .05       0
Bank Sta=4979.3,5010.8
XS Rating Curve= 0 ,0
Exp/Cntr=0.3,0.1

Type RM Length L Ch R = 1 ,268     ,0,0,0
BEGIN DESCRIPTION:
LITTLE LLANO 005 1.0
END DESCRIPTION:
XS GIS Cut Line= 4
      2875055.69     10234503.08      2875099.85     10233947.36
      2874830.31     10233834.08      2874334.22     10233841.89
#Sta/Elev= 30
  4291.8  939.94  4392.1  937.86  4462.3  934.91  4542.6  935.42  4592.7  934.61
  4723.1  930.31  4793.3  929.54  4854.2  927.46  4886.3  924.72    4930  924.58
  4948.3  925.42  4953.7  924.83  4962.3  926.13    4984  925.44 4994.46  920.21
 5018.62  920.17 5025.22  920.43  5059.9  925.07  5114.1   927.5  5216.3  928.36
  5306.3  930.21  5386.3  933.63  5436.3  936.95  5536.3  941.25  5556.3  941.64
  5566.3   941.2  5596.3   942.6  5606.3  942.31  5616.3  943.25  5637.8  943.37
#Mann= 3 , 0 , 0
  4291.8     .05       0    4984     .03       0  5059.9     .05       0
Bank Sta=4984,5059.9
XS Rating Curve= 0 ,0
Exp/Cntr=0.3,0.1

Chan Stop Cuts=-1
Use User Specified Reach Order=0
Composite Channel Slope=5