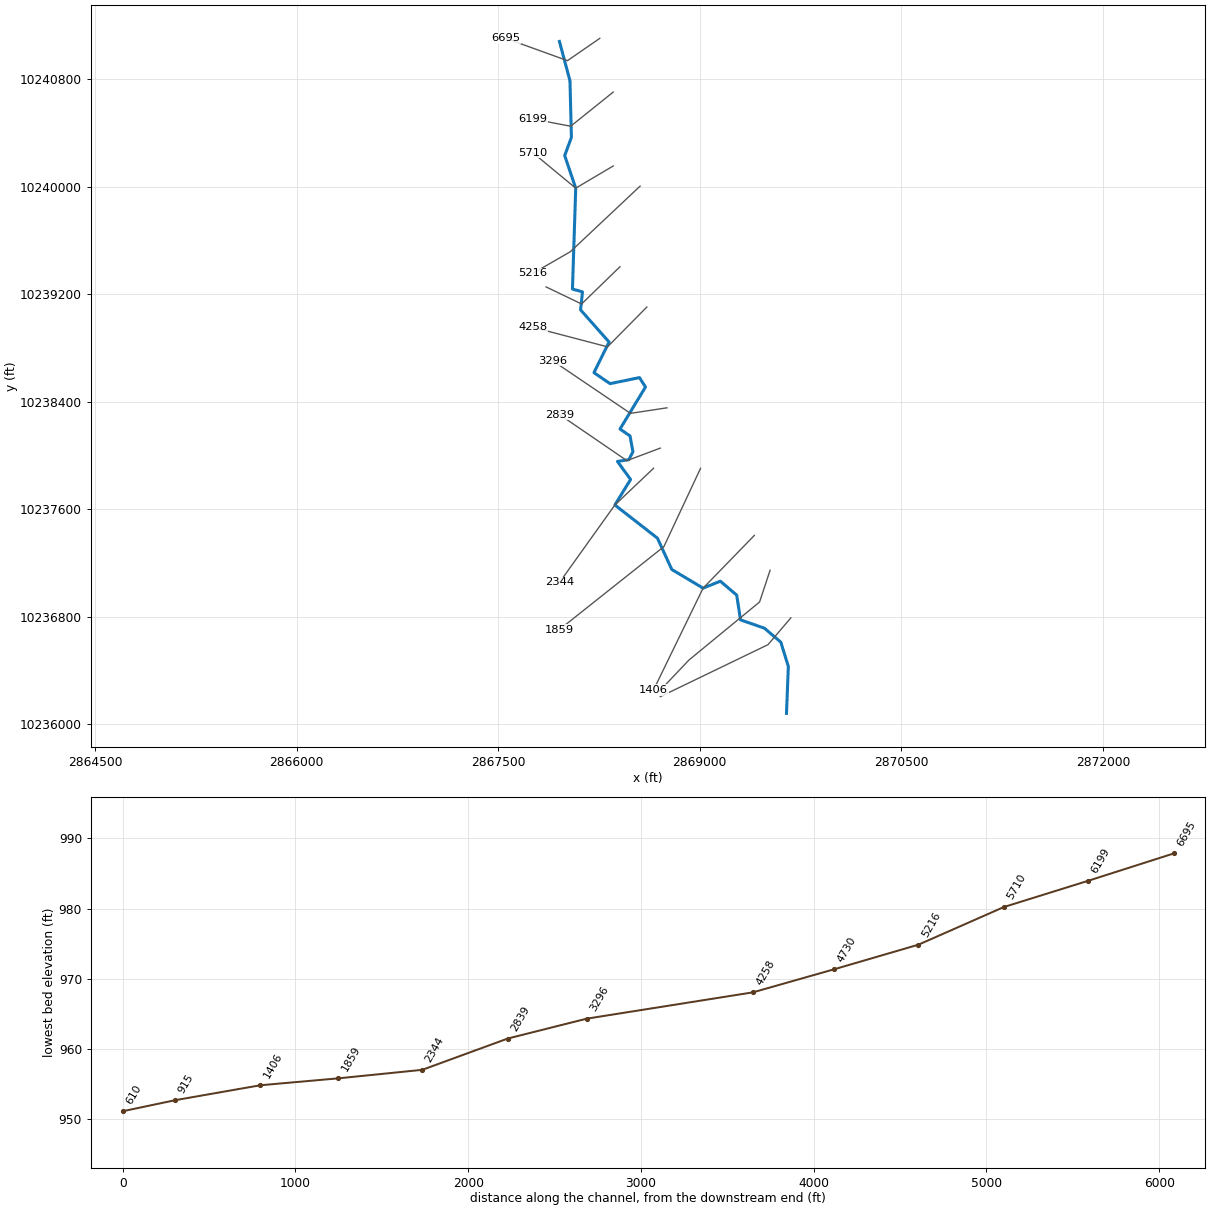
--- LITTLE LLANO 008.prj (project) ---

Proj Title=LITTLE LLANO 008 Base Level Engineering
Current Plan=p01
Default Exp/Contr=0.3,0.1
English Units
Geom File=g01
Flow File=f01
Plan File=p01
Y Axis Title=Elevation
X Axis Title(PF)=Main Channel Distance
X Axis Title(XS)=Station
BEGIN DESCRIPTION:
LITTLE LLANO 008
END DESCRIPTION:
DSS Export Rating Curves= 0
DSS Export Rating Curve Sorted= 0
DSS Export Volume Flow Curves= 0
DXF OffsetX= 0
DXF OffsetY= 0
DXF ScaleX= 1
DXF ScaleY= 10

--- LITTLE LLANO 008.p01 (plan) ---

Plan Title=Multiple Run
Short Identifier=Multiple
Geom File=g01
Flow File=f01
Subcritical Flow
K Sum by GR= 0
Std Step Tol= 0.01
Critical Tol= 0.01
Num of Std Step Trials= 20
Max Error Tol= 0.3
Flow Tol Ratio= 0.001
Split Flow NTrial= 30
Split Flow Tol= 0.02
Split Flow Ratio= 0.02
Log Output Level= 0
Friction Slope Method= 1
Unsteady Friction Slope Method= 2
Unsteady Bridges Friction Slope Method= 1
Parabolic Critical Depth
Global Vel Dist=  1 , 1 , 1
Global Log Level= 0
CheckData=True
Encroach Param= -1, 0, 0, 0
BEGIN DESCRIPTION:
Multiple Run
END DESCRIPTION:

--- LITTLE LLANO 008.f01 (steady flow) ---

Flow Title=Multiple
Number of Profiles=7
Profile Names=10-year,25-year,50-year,1pct_min,100-year,1pct_plu,500-year
River Rch & RM= LITTLE LLANO 008,Reach-1,6695
     392     628     919     726    1230    2086    1700
River Rch & RM= LITTLE LLANO 008,Reach-1,1859
     474     771    1084     816    1454    2591    2005
Boundary for River Rch & Prof#=LITTLE LLANO 008,Reach-1,1
Up Type=0
Dn Type=3
Dn Slope=0.005
Boundary for River Rch & Prof#=LITTLE LLANO 008,Reach-1,2
Up Type=0
Dn Type=3
Dn Slope=0.005
Boundary for River Rch & Prof#=LITTLE LLANO 008,Reach-1,3
Up Type=0
Dn Type=3
Dn Slope=0.005
Boundary for River Rch & Prof#=LITTLE LLANO 008,Reach-1,4
Up Type=0
Dn Type=3
Dn Slope=0.005
Boundary for River Rch & Prof#=LITTLE LLANO 008,Reach-1,5
Up Type=0
Dn Type=3
Dn Slope=0.005
Boundary for River Rch & Prof#=LITTLE LLANO 008,Reach-1,6
Up Type=0
Dn Type=3
Dn Slope=0.005
Boundary for River Rch & Prof#=LITTLE LLANO 008,Reach-1,7
Up Type=0
Dn Type=3
Dn Slope=0.005

--- LITTLE LLANO 008.g01 (geometry) ---

Geom Title=Existing Conditions
Program Version=4.10

River Reach=LITTLE LLANO 008,Reach-1
Reach XY= 30
      2867955.25       10241080.      2868033.75       10240787.
       2868044.5       10240366.       2867994.5       10240231.
       2868076.5       10239988.      2868052.25       10239237.
      2868126.75       10239216.      2868112.75       10239082.
      2868324.75       10238843.      2868212.25       10238615.
      2868331.75       10238533.        2868551.       10238578.
      2868595.75       10238508.        2868406.       10238195.
      2868480.75       10238144.      2868502.25       10238026.
       2868471.5       10237967.        2868387.       10237954.
        2868485.       10237820.        2868368.       10237630.
      2868684.75       10237383.       2868791.5       10237150.
       2869024.5       10237011.      2869152.75       10237063.
      2869274.75       10236959.        2869303.       10236775.
        2869481.       10236713.        2869603.       10236609.
        2869659.       10236428.      2869645.25       10236079.

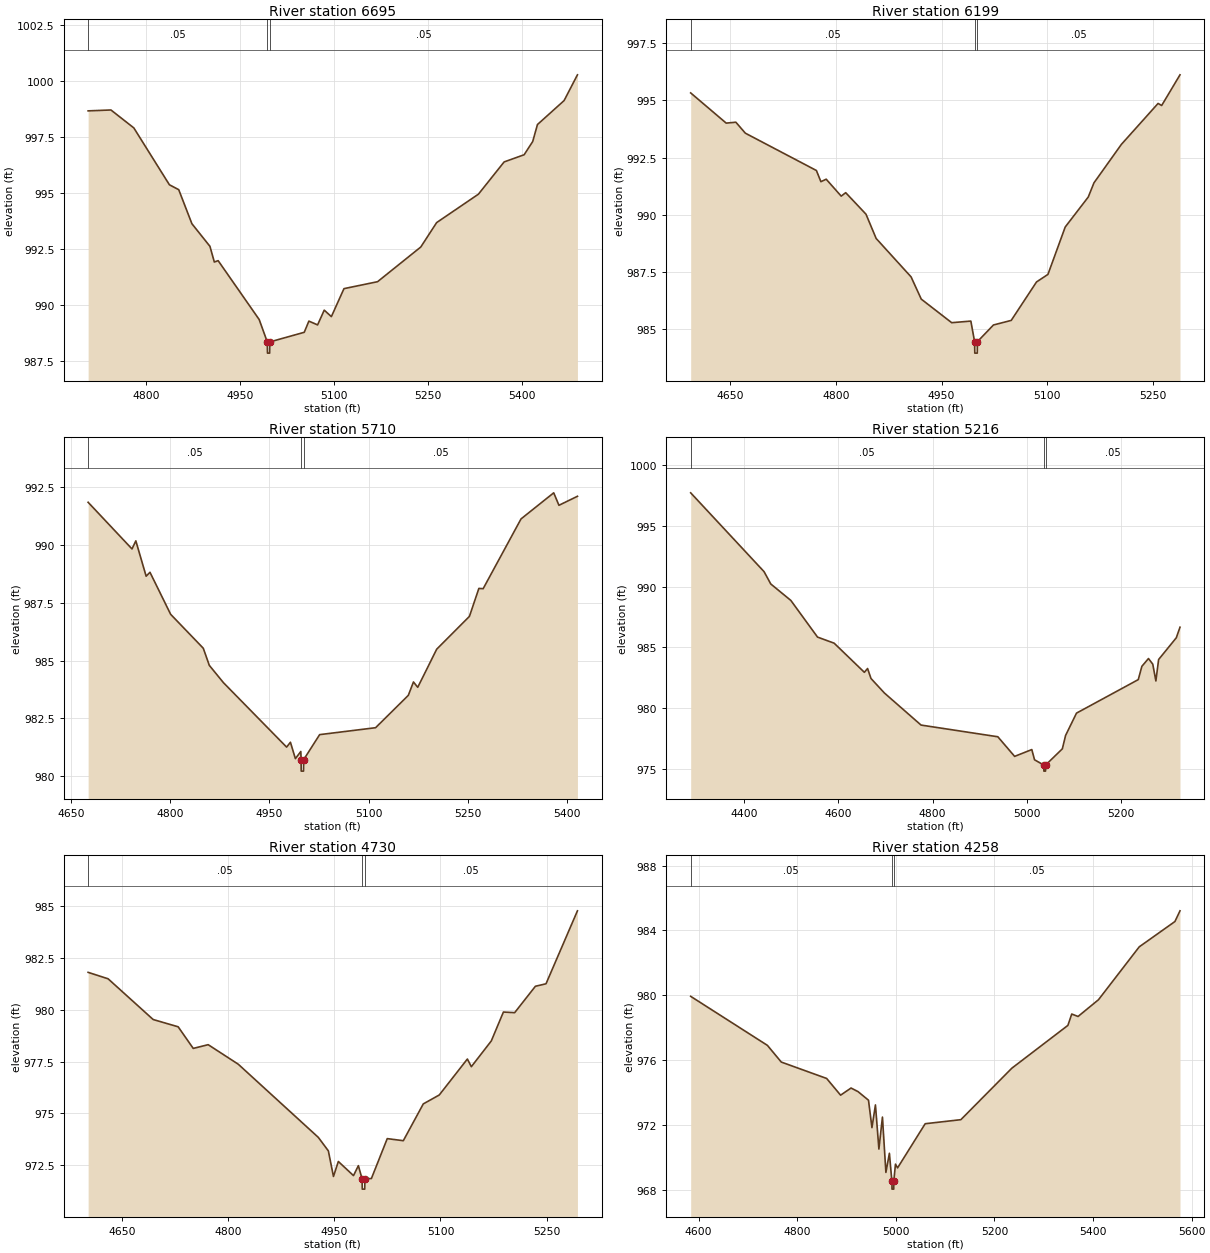
Type RM Length L Ch R = 1 ,6695    ,496,496,496
BEGIN DESCRIPTION:
LITTLE LLANO 008 12.0
END DESCRIPTION:
XS GIS Cut Line= 3
      2868255.65     10241103.09      2868015.25       10240937.
      2867555.65     10241103.12
#Sta/Elev= 30
  4707.8  998.68  4744.2  998.72  4780.7  997.92  4837.5  995.38  4852.4  995.16
  4873.4  993.64  4902.2  992.63  4909.2  991.93  4915.3  991.99  4980.8  989.36
  4993.7  988.36    4994  987.86  4997.5  987.86  4997.7  988.36  5052.7  988.79
  5060.1  989.29    5074  989.12  5084.6  989.78    5096  989.49  5116.1  990.74
  5169.7  991.05  5238.7   992.6    5264  993.69  5330.7  994.96  5371.7   996.4
  5403.6  996.72  5417.3  997.31  5424.9  998.07  5467.4  999.14  5488.7 1000.29
#Mann= 3 ,-1 , 0
  4707.8     .05       0  4993.7     .03       0  4997.7     .05       0
Bank Sta=4993.7,4997.7
XS Rating Curve= 0 ,0
Exp/Cntr=0.3,0.1

Type RM Length L Ch R = 1 ,6199    ,489,489,489
BEGIN DESCRIPTION:
LITTLE LLANO 008 11.0
END DESCRIPTION:
XS GIS Cut Line= 3
      2868355.66     10240703.09        2868039.       10240449.
      2867755.72      10240503.1
#Sta/Elev= 30
    4594  995.33  4644.4  994.01  4658.1  994.05  4671.6  993.57  4772.4  991.94
  4778.8  991.45  4786.3  991.56  4807.6  990.82    4814  990.97  4842.8  990.03
  4857.2  988.97  4906.8  987.29  4921.2  986.32  4964.4  985.29  4991.6  985.36
  4996.9  984.46  4997.2  983.96  5000.7  983.96  5000.9  984.46  5023.7  985.19
  5048.9  985.39  5084.8  987.07    5101   987.4  5125.5  989.47  5158.2  990.78
  5166.3   991.4  5205.2  993.08  5257.3  994.87  5262.4  994.78  5288.4  996.12
#Mann= 3 ,-1 , 0
    4594     .05       0  4996.9     .03       0  5000.9     .05       0
Bank Sta=4996.9,5000.9
XS Rating Curve= 0 ,0
Exp/Cntr=0.3,0.1

Type RM Length L Ch R = 1 ,5710    ,494,494,494
BEGIN DESCRIPTION:
LITTLE LLANO 008 10.0
END DESCRIPTION:
XS GIS Cut Line= 3
      2868355.72     10240153.13       2868076.5       10239988.
      2867755.67     10240253.12
#Sta/Elev= 30
  4675.6  991.85    4742  989.83  4747.8  990.18  4763.4  988.65  4769.2  988.82
  4800.5     987  4849.9  985.53    4859  984.79  4880.4  984.04    4976  981.25
  4981.8  981.46  4989.3  980.75  4997.5  981.06  4997.9  980.71  4998.1  980.21
  5001.6  980.21  5001.9  980.71    5026  981.79  5110.7  982.09  5160.2  983.49
    5168  984.07  5174.5  983.84  5203.2  985.49  5252.7  986.91    5267  988.12
  5273.5  988.11  5330.8  991.13  5380.3  992.26  5388.2  991.72  5416.2  992.11
#Mann= 3 ,-1 , 0
  4675.6     .05       0  4997.9     .03       0  5001.9     .05       0
Bank Sta=4997.9,5001.9
XS Rating Curve= 0 ,0
Exp/Cntr=0.3,0.1

Type RM Length L Ch R = 1 ,5216    ,486,486,486
BEGIN DESCRIPTION:
LITTLE LLANO 008 9.0
END DESCRIPTION:
XS GIS Cut Line= 3
      2868555.67      10240003.1      2868036.75       10239515.
      2867755.64     10239353.09
#Sta/Elev= 30
  4287.6  997.69  4443.1  991.22  4457.3  990.21  4499.8  988.86  4556.4  985.85
  4591.6  985.35  4655.6  982.96  4662.4  983.27  4669.7  982.45  4698.1  981.26
  4775.7  978.63  4938.4  977.67    4974  976.06  5010.4  976.62  5016.2  975.78
  5035.7  975.35    5036  974.85  5039.5  974.85  5039.7  975.35  5075.1  976.68
    5082  977.78  5105.1  979.61    5236  982.36  5243.6  983.45  5257.6  984.09
  5266.7  983.63  5273.3  982.25  5279.1  984.01  5316.5  985.79  5324.4  986.66
#Mann= 3 ,-1 , 0
  4287.6     .05       0  5035.7     .03       0  5039.7     .05       0
Bank Sta=5035.7,5039.7
XS Rating Curve= 0 ,0
Exp/Cntr=0.3,0.1

Type RM Length L Ch R = 1 ,4730    ,472,472,472
BEGIN DESCRIPTION:
LITTLE LLANO 008 8.0
END DESCRIPTION:
XS GIS Cut Line= 3
      2868405.67      10239403.1      2868120.25       10239126.
       2867855.7      10239253.1
#Sta/Elev= 30
  4602.2  981.79  4630.4  981.48  4694.1  979.52  4729.4  979.17  4750.7  978.13
  4771.8  978.31  4814.3  977.37  4927.4  973.85  4941.6   973.2  4948.8  971.97
  4955.7  972.69  4977.1  972.01    4984  972.49  4989.2  971.86  4989.5  971.36
    4993  971.36  4993.2  971.86  5002.4  971.87  5024.8  973.79  5047.5  973.69
  5075.7  975.46  5098.3  975.89    5138  977.62  5143.6  977.25  5171.8  978.49
  5188.9  979.88  5204.8  979.85  5234.1  981.12  5249.1  981.24  5293.5  984.75
#Mann= 3 ,-1 , 0
  4602.2     .05       0  4989.2     .03       0  4993.2     .05       0
Bank Sta=4989.2,4993.2
XS Rating Curve= 0 ,0
Exp/Cntr=0.3,0.1

Type RM Length L Ch R = 1 ,4258    ,962,962,962
BEGIN DESCRIPTION:
LITTLE LLANO 008 7.0
END DESCRIPTION:
XS GIS Cut Line= 3
       2868605.7     10239103.13      2868313.25       10238807.
      2867755.68     10238953.11
#Sta/Elev= 30
  4583.8  979.94  4739.4  976.92  4767.6  975.89  4859.6  974.88  4887.9  973.85
  4909.1  974.29  4923.2  974.07  4944.5  973.54  4951.5  971.85  4958.6  973.25
  4965.6  970.53  4972.8   972.5  4979.8  969.09  4986.9  970.27  4991.9  968.56
  4992.2  968.06  4995.7  968.06  4995.9  968.56  4999.2   969.6  5003.5  969.37
  5059.5  972.09  5131.9  972.34  5235.2  975.51    5349  978.15  5356.8  978.85
  5369.6   978.7    5411  979.73  5493.7  982.99  5566.1  984.55  5576.4  985.21
#Mann= 3 ,-1 , 0
  4583.8     .05       0  4991.9     .03       0  4995.9     .05       0
Bank Sta=4991.9,4995.9
XS Rating Curve= 0 ,0
Exp/Cntr=0.3,0.1

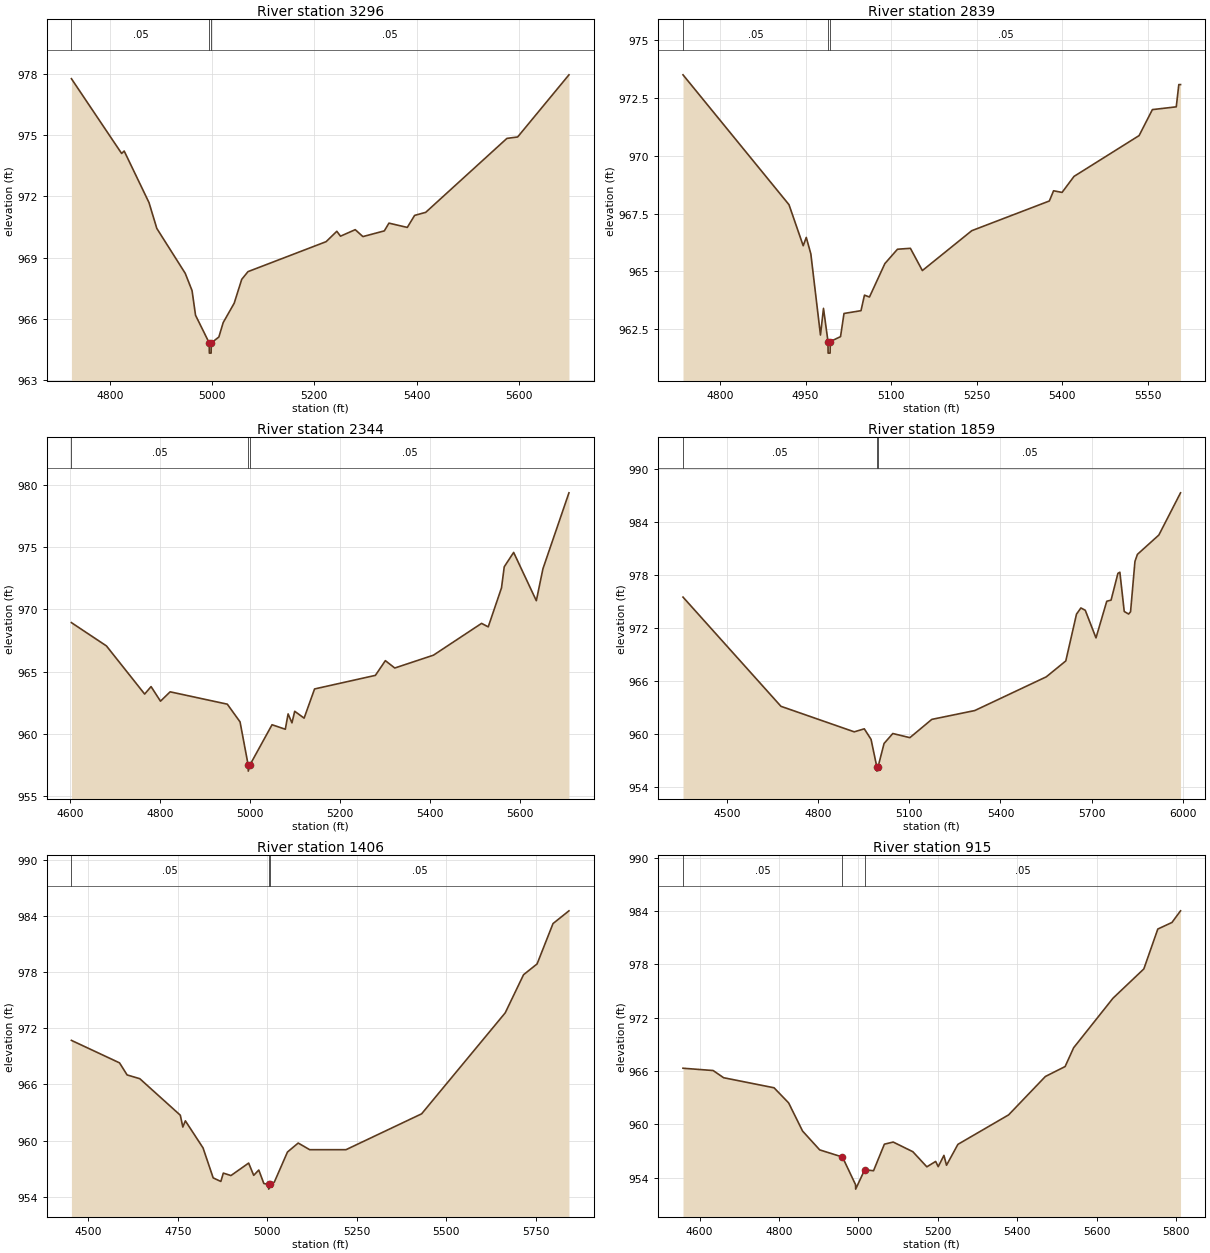
Type RM Length L Ch R = 1 ,3296    ,457,457,457
BEGIN DESCRIPTION:
LITTLE LLANO 008 6.0
END DESCRIPTION:
XS GIS Cut Line= 3
      2868755.66     10238353.11      2868483.75       10238312.
      2867905.72     10238703.09
#Sta/Elev= 30
    4725  977.78  4823.2  974.11  4828.2  974.23  4876.7   971.7    4892  970.43
  4947.5  968.23  4960.9  967.38  4967.7  966.17  4994.5  964.81  4994.7  964.31
  4998.2  964.31  4998.5  964.81  5013.3   965.1  5021.8  965.81  5043.3  966.76
    5058  967.93  5070.3  968.31    5223  969.78    5244  970.29  5251.2  970.05
    5280  970.37    5295  970.03  5336.9  970.31  5345.9  970.69  5381.8  970.48
  5396.1  971.07  5417.8  971.22  5576.6  974.85  5597.6  974.92  5697.9  977.97
#Mann= 3 ,-1 , 0
    4725     .05       0  4994.5     .03       0  4998.5     .05       0
Bank Sta=4994.5,4998.5
XS Rating Curve= 0 ,0
Exp/Cntr=0.3,0.1

Type RM Length L Ch R = 1 ,2839    ,495,495,495
BEGIN DESCRIPTION:
LITTLE LLANO 008 5.0
END DESCRIPTION:
XS GIS Cut Line= 3
      2868705.71     10238053.12       2868457.5       10237960.
      2867955.69     10238303.11
#Sta/Elev= 30
  4734.9  973.48  4920.9  967.88  4945.8  966.11  4951.2  966.47  4959.2  965.76
  4976.1  962.26  4981.4  963.41  4989.3  961.98  4989.5  961.48    4993  961.48
  4993.3  961.98  5011.3  962.19  5017.4  963.19  5047.2  963.31  5053.3  963.98
  5062.1   963.9  5089.1  965.34  5111.2  965.96  5133.9     966  5154.9  965.04
  5241.6  966.76  5377.7  968.04  5385.1  968.48    5400  968.41    5421   969.1
  5535.2  970.86  5558.5  971.98  5600.4   972.1  5604.9  973.06  5607.9  973.06
#Mann= 3 ,-1 , 0
  4734.9     .05       0  4989.3     .03       0  4993.3     .05       0
Bank Sta=4989.3,4993.3
XS Rating Curve= 0 ,0
Exp/Cntr=0.3,0.1

Type RM Length L Ch R = 1 ,2344    ,485,485,485
BEGIN DESCRIPTION:
LITTLE LLANO 008 4.0
END DESCRIPTION:
XS GIS Cut Line= 3
       2868655.7     10237903.13        2868368.       10237630.
      2867955.68      10237053.1
#Sta/Elev= 30
  4603.3  968.93  4681.2  967.06  4766.1   963.2  4780.3   963.8  4801.3  962.63
  4822.7  963.38  4949.8  962.39  4978.1  960.97  4996.1  957.52  4996.4  957.02
  5000.1  957.52  5049.2  960.74  5078.7  960.38  5084.9  961.61  5093.5  960.89
  5099.6  961.82  5120.5  961.27  5143.7  963.61  5278.9   964.7  5301.1  965.88
    5322  965.29    5408  966.32  5514.9  968.87  5529.7  968.59  5559.2  971.72
  5565.3  973.41  5586.2  974.56  5636.6  970.69  5651.3  973.25  5709.1  979.34
#Mann= 3 ,-1 , 0
  4603.3     .05       0  4996.1     .03       0  5000.1     .05       0
Bank Sta=4996.1,5000.1
XS Rating Curve= 0 ,0
Exp/Cntr=0.3,0.1

Type RM Length L Ch R = 1 ,1859    ,453,453,453
BEGIN DESCRIPTION:
LITTLE LLANO 008 3.0
END DESCRIPTION:
XS GIS Cut Line= 3
      2869005.67     10237903.09      2868732.75       10237320.
      2867955.65     10236703.09
#Sta/Elev= 30
  4356.2  975.52  4678.3  963.15  4919.3  960.26  4952.3   960.6  4974.5  959.41
  4993.4  956.31  4993.7  955.81  4997.7  956.31  5017.3  958.94  5046.1  960.07
  5102.2   959.6  5174.3  961.67  5315.5  962.67  5550.8  966.49  5614.9  968.29
  5650.1  973.59  5664.5  974.29  5678.9  974.03  5714.2   970.9  5749.6  975.05
  5763.8  975.18  5786.3  978.21  5792.7  978.34  5807.1  973.89  5821.5   973.6
  5827.9  973.87  5842.3  979.56  5850.4  980.36  5920.9  982.55  5992.2  987.33
#Mann= 3 ,-1 , 0
  4356.2     .05       0  4993.4     .03       0  4997.7     .05       0
Bank Sta=4993.4,4997.7
XS Rating Curve= 0 ,0
Exp/Cntr=0.3,0.1

Type RM Length L Ch R = 1 ,1406    ,491,491,491
BEGIN DESCRIPTION:
LITTLE LLANO 008 2.0
END DESCRIPTION:
XS GIS Cut Line= 3
      2869405.71     10237403.14       2869024.5       10237011.
      2868655.67     10236253.08
#Sta/Elev= 30
  4453.1   970.7  4587.5   968.3  4608.7  967.01  4644.1  966.61  4757.3  962.71
  4764.3  961.45  4771.4  962.11  4820.8  959.22  4849.1  956.02  4870.5  955.64
  4877.4  956.53  4898.8  956.27  4948.2   957.6  4962.3  956.29  4976.5  956.86
  4990.6  955.42  5003.8  955.32  5004.1  954.82  5008.2  955.32  5019.9  955.57
  5056.6  958.78  5086.6  959.74  5118.7  959.03  5220.1  959.03  5431.4  962.86
  5664.9  973.64  5716.1  977.71  5753.9  978.86  5798.4  983.17  5842.9  984.53
#Mann= 3 ,-1 , 0
  4453.1     .05       0  5003.8     .03       0  5008.2     .05       0
Bank Sta=5003.8,5008.2
XS Rating Curve= 0 ,0
Exp/Cntr=0.3,0.1

Type RM Length L Ch R = 1 ,915     ,305,305,305
BEGIN DESCRIPTION:
Mapping XS bd70b080
END DESCRIPTION:
XS GIS Cut Line= 4
      2869523.17     10237144.22      2869445.04     10236908.08
        2868919.     10236475.79      2868696.77      10236241.4
#Sta/Elev= 30
  4558.2  966.31  4634.1  966.05  4660.5  965.24  4787.4  964.11  4824.1  962.41
  4859.2  959.24  4902.3  957.12  4959.7  956.31  4992.6   953.2  4992.9   952.7
  5015.6  954.88  5037.9  954.77  5065.2  957.76  5087.4     958  5136.9  956.91
  5172.1  955.21  5194.3  955.82  5200.8  955.23  5215.1   956.5  5221.6  955.39
  5250.3  957.74    5378  961.06  5470.5  965.38  5520.2   966.5  5541.6  968.61
  5640.7  974.19  5718.4  977.49  5753.6  981.98  5789.2  982.72  5810.8  984.03
#Mann= 3 , 0 , 0
  4558.2     .05       0  4959.7     .03       0  5015.6     .05       0
Bank Sta=4959.7,5015.6
XS Rating Curve= 0 ,0
Exp/Cntr=0.3,0.1

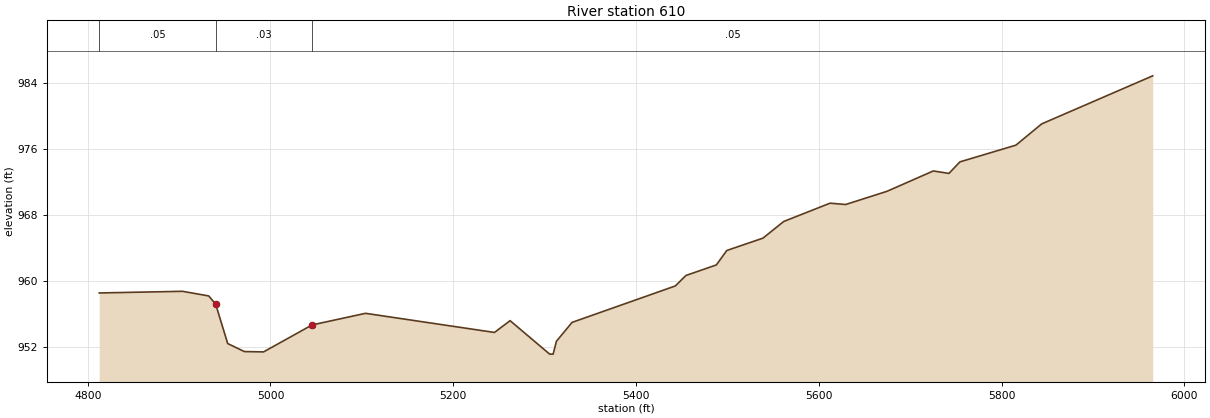
Type RM Length L Ch R = 1 ,610     ,0,0,0
BEGIN DESCRIPTION:
LITTLE LLANO 008 1.0
END DESCRIPTION:
XS GIS Cut Line= 3
       2869677.7     10236790.05      2869507.54     10236590.37
       2868705.7     10236203.12
#Sta/Elev= 30
  4812.6  958.54  4903.8  958.74  4932.4  958.18    4940  957.19  4953.2   952.4
 4971.46  951.43 4992.44  951.39  5045.5  954.66    5104  956.07  5245.1  953.75
  5262.2  955.18  5305.5  951.12  5309.3  951.12  5312.9  952.68    5330  954.97
    5443  959.39  5454.6  960.66  5487.9  961.94  5499.3  963.69  5538.9  965.19
  5561.6  967.21  5612.3  969.43  5629.4  969.27  5674.6  970.87  5725.3  973.34
  5742.4  973.04  5754.4  974.44  5815.7  976.47  5843.9  979.05  5965.4  984.88
#Mann= 3 , 0 , 0
  4812.6     .05       0    4940     .03       0  5045.5     .05       0
Bank Sta=4940,5045.5
XS Rating Curve= 0 ,0
Exp/Cntr=0.3,0.1

Chan Stop Cuts=-1
Use User Specified Reach Order=0
Composite Channel Slope=5