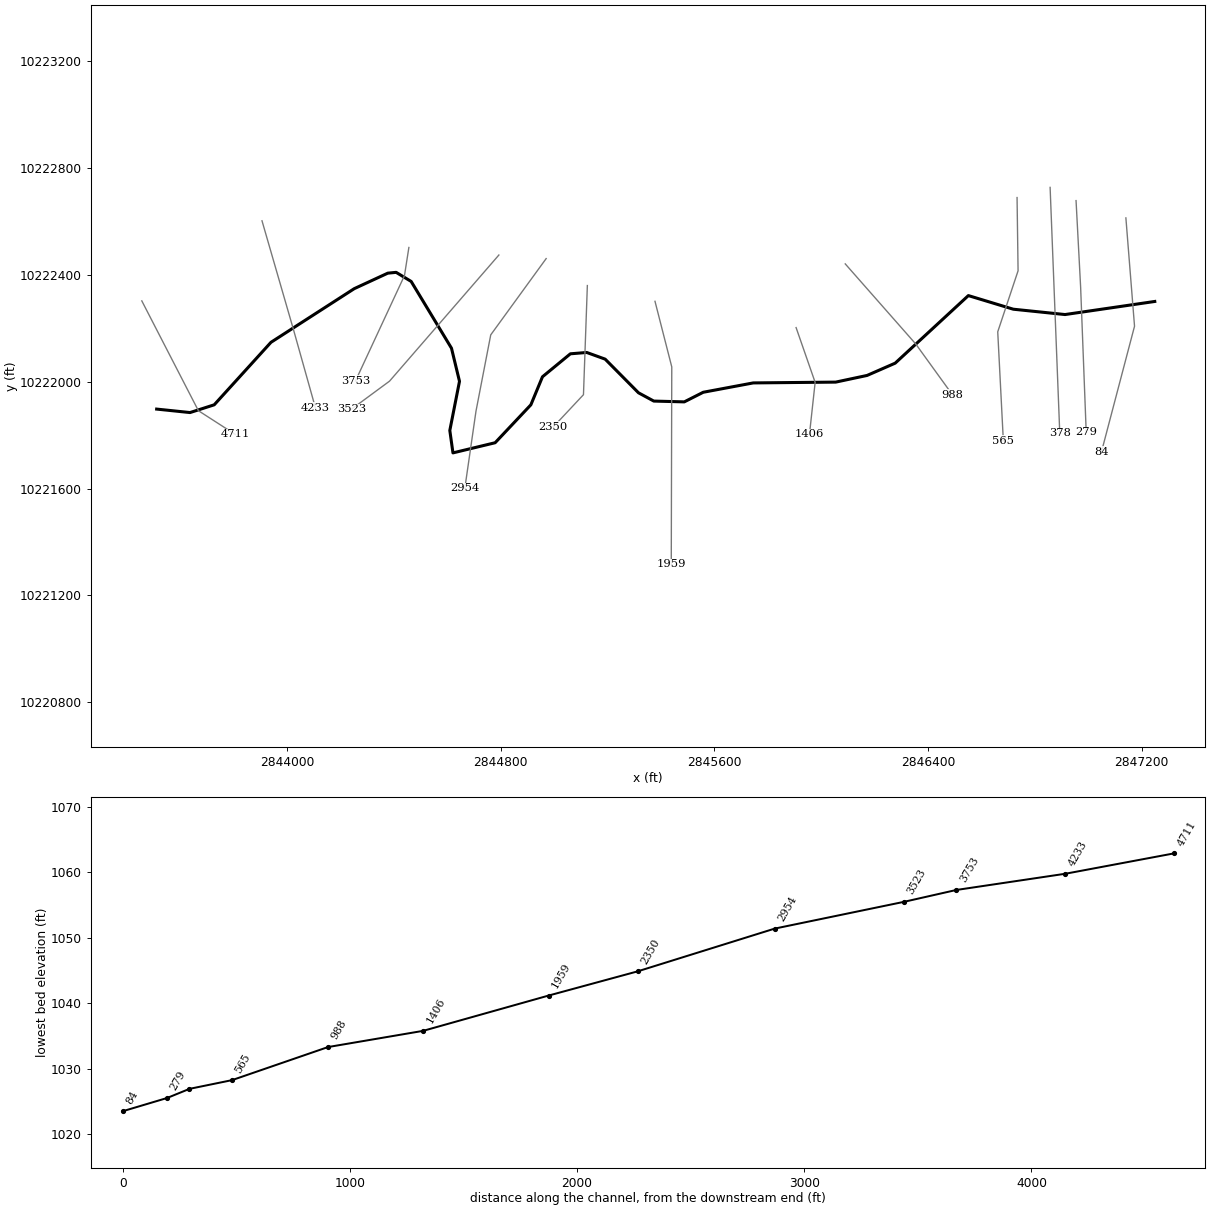
--- LITTLE LLANO 010.prj (project) ---

Proj Title=LITTLE LLANO 010 Base Level Engineering
Current Plan=p01
Default Exp/Contr=0.3,0.1
English Units
Geom File=g01
Flow File=f01
Plan File=p01
Y Axis Title=Elevation
X Axis Title(PF)=Main Channel Distance
X Axis Title(XS)=Station
BEGIN DESCRIPTION:
LITTLE LLANO 010
END DESCRIPTION:
DSS Export Rating Curves= 0
DSS Export Rating Curve Sorted= 0
DSS Export Volume Flow Curves= 0
DXF OffsetX= 0
DXF OffsetY= 0
DXF ScaleX= 1
DXF ScaleY= 10

--- LITTLE LLANO 010.p01 (plan) ---

Plan Title=Multiple Run
Short Identifier=Multiple
Geom File=g01
Flow File=f01
Subcritical Flow
K Sum by GR= 0
Std Step Tol= 0.01
Critical Tol= 0.01
Num of Std Step Trials= 20
Max Error Tol= 0.3
Flow Tol Ratio= 0.001
Split Flow NTrial= 30
Split Flow Tol= 0.02
Split Flow Ratio= 0.02
Log Output Level= 0
Friction Slope Method= 1
Unsteady Friction Slope Method= 2
Unsteady Bridges Friction Slope Method= 1
Parabolic Critical Depth
Global Vel Dist=  1 , 1 , 1
Global Log Level= 0
CheckData=True
Encroach Param= -1, 0, 0, 0
BEGIN DESCRIPTION:
Multiple Run
END DESCRIPTION:

--- LITTLE LLANO 010.f01 (steady flow) ---

Flow Title=Multiple
Number of Profiles=7
Profile Names=10-year,25-year,50-year,1pct_min,100-year,1pct_plu,500-year
River Rch & RM= LITTLE LLANO 010,Reach-1,4711
     816    1375    3720    2975    5498   10162    8198
Boundary for River Rch & Prof#=LITTLE LLANO 010,Reach-1,1
Up Type=0
Dn Type=3
Dn Slope=0.005
Boundary for River Rch & Prof#=LITTLE LLANO 010,Reach-1,2
Up Type=0
Dn Type=3
Dn Slope=0.005
Boundary for River Rch & Prof#=LITTLE LLANO 010,Reach-1,3
Up Type=0
Dn Type=3
Dn Slope=0.005
Boundary for River Rch & Prof#=LITTLE LLANO 010,Reach-1,4
Up Type=0
Dn Type=3
Dn Slope=0.005
Boundary for River Rch & Prof#=LITTLE LLANO 010,Reach-1,5
Up Type=0
Dn Type=3
Dn Slope=0.005
Boundary for River Rch & Prof#=LITTLE LLANO 010,Reach-1,6
Up Type=0
Dn Type=3
Dn Slope=0.005
Boundary for River Rch & Prof#=LITTLE LLANO 010,Reach-1,7
Up Type=0
Dn Type=3
Dn Slope=0.005

--- LITTLE LLANO 010.g01 (geometry) ---

Geom Title=Existing Conditions
Program Version=4.10

River Reach=LITTLE LLANO 010,Reach-1
Reach XY= 30
      2843511.25       10221898.      2843636.25       10221885.
      2843726.75       10221914.      2843939.25       10222148.
      2844251.25       10222349.      2844376.75       10222407.
        2844408.       10222410.      2844464.25       10222376.
      2844615.25       10222126.      2844645.25       10222002.
        2844609.       10221818.      2844620.75       10221734.
      2844778.75       10221772.       2844912.5       10221914.
        2844956.       10222019.       2845060.5       10222105.
      2845121.75       10222110.      2845190.75       10222085.
       2845315.5       10221959.      2845372.75       10221928.
        2845487.       10221925.        2845558.       10221961.
      2845745.25       10221996.        2846054.       10221999.
       2846171.5       10222024.      2846276.75       10222070.
      2846550.75       10222323.        2846719.       10222272.
      2846912.75       10222252.      2847248.75       10222301.

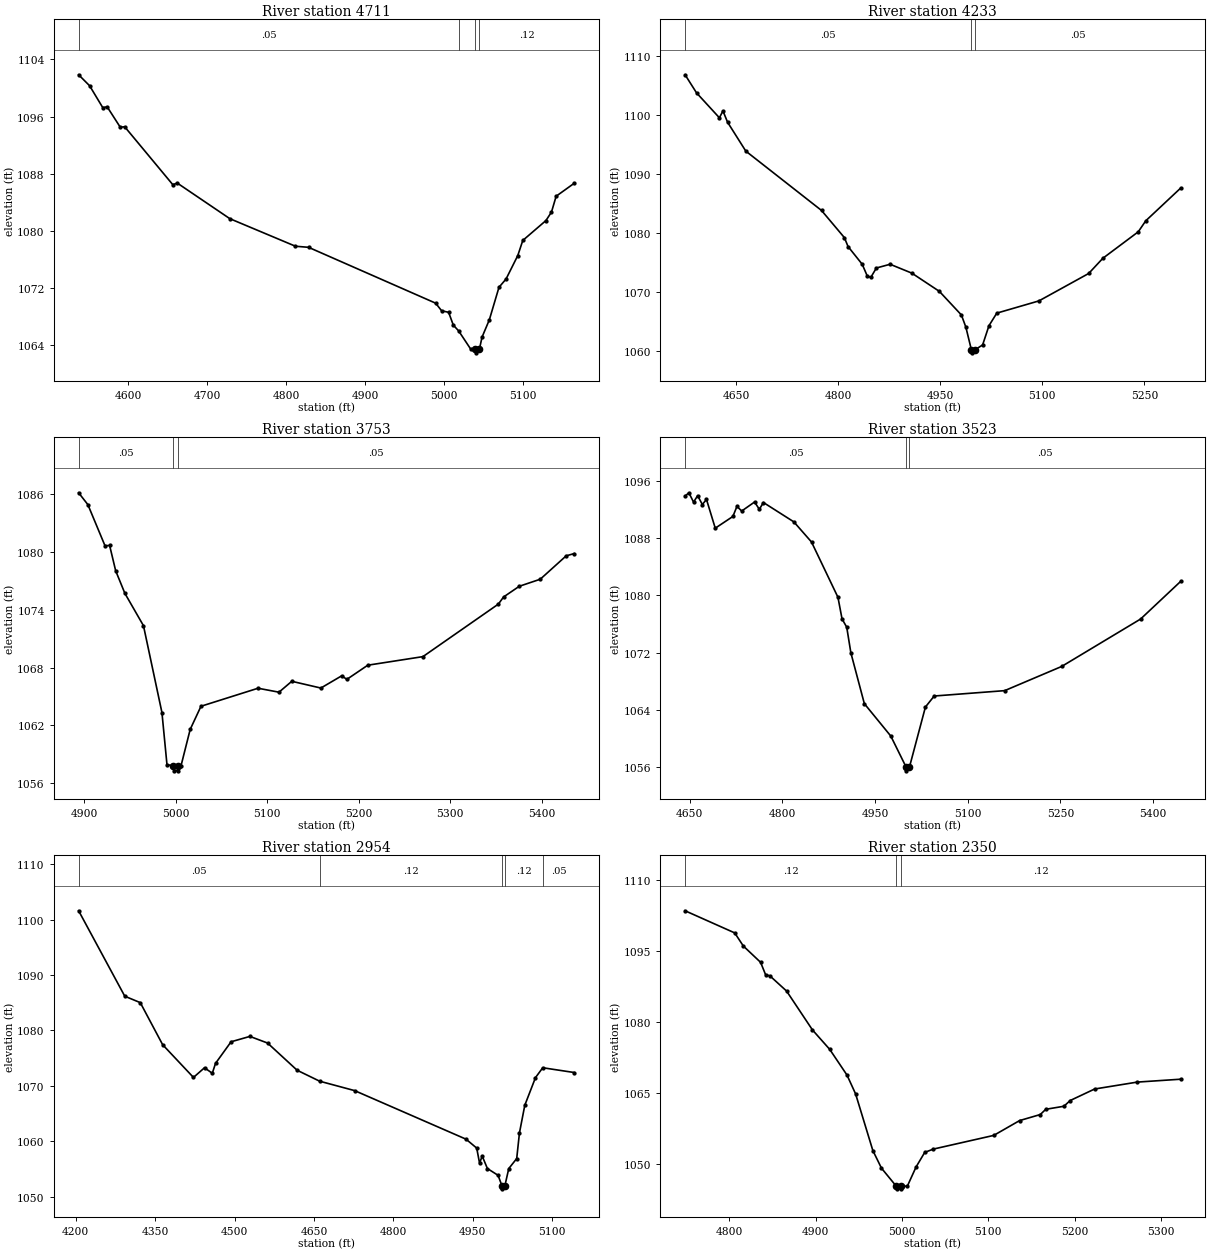
Type RM Length L Ch R = 1 ,4711    ,478,478,478
BEGIN DESCRIPTION:
LITTLE LLANO 010 10.0
END DESCRIPTION:
XS GIS Cut Line= 3
      2843455.67     10222303.14       2843667.5       10221892.
      2843805.68     10221803.11
#Sta/Elev= 30
  4537.5 1101.85  4551.4 1100.31    4568 1097.25  4573.6 1097.36  4590.1 1094.51
  4595.8 1094.56  4656.6 1086.45  4662.3 1086.67  4728.8 1081.68  4811.8 1077.82
  4828.3 1077.67  4989.1 1069.84  4996.6 1068.78  5005.5 1068.56  5011.4 1066.77
  5018.2 1065.95  5033.5 1063.39  5039.3 1063.38  5039.7 1062.88  5044.4 1063.38
  5047.8 1065.09    5057 1067.51  5069.2 1072.07  5078.1 1073.22    5093 1076.52
  5099.3 1078.63  5128.6 1081.42  5135.6 1082.61  5141.5 1084.83  5164.3 1086.64
#Mann= 4 ,-1 , 0
  4537.5     .05       0  5018.2     .12       0  5039.3     .05       0
  5044.4     .12       0
Bank Sta=5039.3,5044.4
XS Rating Curve= 0 ,0
Exp/Cntr=0.3,0.1

Type RM Length L Ch R = 1 ,4233    ,480,480,480
BEGIN DESCRIPTION:
LITTLE LLANO 010 9.0
END DESCRIPTION:
XS GIS Cut Line= 3
       2843905.7     10222603.07      2844023.75       10222195.
      2844105.69     10221903.08
#Sta/Elev= 30
  4575.2 1106.83    4592 1103.77  4625.6 1099.55  4630.8 1100.72  4637.6  1098.8
  4664.4 1093.91  4775.6 1083.87  4809.2 1079.27  4814.6 1077.76  4835.4 1074.76
  4842.8 1072.78    4848 1072.53  4856.2 1074.13  4876.4 1074.76  4908.3 1073.26
  4948.8 1070.17  4981.1 1066.18  4987.7 1064.11  4995.8 1060.27  4996.2 1059.77
  5000.9 1060.27  5012.3 1061.11  5021.6 1064.36  5033.1 1066.49    5095 1068.56
  5168.1  1073.2  5188.9 1075.77  5240.9 1080.25    5252 1082.12  5303.2 1087.65
#Mann= 3 ,-1 , 0
  4575.2     .05       0  4995.8     .03       0  5000.9     .05       0
Bank Sta=4995.8,5000.9
XS Rating Curve= 0 ,0
Exp/Cntr=0.3,0.1

Type RM Length L Ch R = 1 ,3753    ,230,230,230
BEGIN DESCRIPTION:
LITTLE LLANO 010 8.0
END DESCRIPTION:
XS GIS Cut Line= 3
      2844455.69     10222503.12      2844439.25       10222398.
      2844255.67     10222003.08
#Sta/Elev= 30
  4893.6 1086.14  4903.7 1084.91  4922.4 1080.65  4927.5 1080.67  4934.1 1078.05
  4944.2  1075.7  4964.5 1072.35  4984.7 1063.34  4990.2 1057.94  4997.3 1057.79
  4997.7 1057.29  5002.1 1057.29  5002.5 1057.79  5005.5 1057.79  5015.6 1061.59
  5027.4 1063.99  5089.8 1065.86  5112.7 1065.45  5126.7 1066.58  5158.5 1065.88
  5181.3 1067.15  5186.9 1066.78  5209.8 1068.25  5270.1 1069.14  5352.6 1074.59
  5358.3 1075.33  5375.5 1076.44  5398.4 1077.17  5426.8  1079.6  5435.5 1079.83
#Mann= 3 ,-1 , 0
  4893.6     .05       0  4997.3     .05       0  5002.5     .05       0
Bank Sta=4997.3,5002.5
XS Rating Curve= 0 ,0
Exp/Cntr=0.3,0.1

Type RM Length L Ch R = 1 ,3523    ,569,569,569
BEGIN DESCRIPTION:
Mapping XS d9307902
END DESCRIPTION:
XS GIS Cut Line= 3
      2844792.72     10222474.91      2844383.29     10222002.64
      2844241.07     10221897.84
#Sta/Elev= 30
  4642.8 1093.89  4648.9 1094.35  4656.5 1093.04  4663.1 1093.95  4670.7 1092.71
  4677.4 1093.42  4691.6  1089.4  4720.1 1091.04  4726.7 1092.45  4734.4  1091.8
  4755.2 1093.06  4762.9 1092.04  4769.5 1092.99  4818.8 1090.28  4847.3 1087.47
  4890.1 1079.74  4896.7 1076.72  4904.3 1075.56    4911 1071.97  4932.8 1064.87
  4975.6 1060.34  5000.5 1055.98  5000.9 1055.48  5005.7 1055.98  5031.6  1064.4
  5045.8 1065.94  5159.8 1066.69    5252 1070.07  5379.7  1076.7  5444.5 1081.96
#Mann= 3 ,-1 , 0
  4642.8     .05       0  5000.5     .05       0  5005.7     .05       0
Bank Sta=5000.5,5005.7
XS Rating Curve= 0 ,0
Exp/Cntr=0.3,0.1

Type RM Length L Ch R = 1 ,2954    ,604,604,604
BEGIN DESCRIPTION:
Mapping XS 4b97e67e
END DESCRIPTION:
XS GIS Cut Line= 4
      2844969.79     10222461.55      2844762.23     10222175.92
      2844707.01     10221890.29      2844665.11      10221600.8
#Sta/Elev= 30
  4205.4 1101.61  4292.6 1086.18  4321.9 1085.02  4364.2 1077.42  4422.4 1071.51
  4443.3 1073.26    4458 1072.26  4464.1 1074.05  4493.5 1077.95  4529.1 1078.92
  4562.5 1077.72  4618.3 1072.81  4660.9 1070.83    4727 1069.13  4937.5 1060.36
  4957.7 1058.75  4963.1 1056.03  4968.1 1057.31  4977.9 1055.06  4998.1 1053.83
  5005.6 1051.89    5006 1051.39  5010.8 1051.89  5018.3 1055.05  5033.3 1056.86
  5038.5  1061.5  5048.6 1066.49  5068.8 1071.48  5082.5 1073.26  5141.9  1072.4
#Mann= 5 ,-1 , 0
  4205.4     .05       0  4660.9     .12       0  5005.6     .07       0
  5010.8     .12       0  5082.5     .05       0
Bank Sta=5005.6,5010.8
XS Rating Curve= 0 ,0
Exp/Cntr=0.3,0.1

Type RM Length L Ch R = 1 ,2350    ,391,391,391
BEGIN DESCRIPTION:
LITTLE LLANO 010 5.0
END DESCRIPTION:
XS GIS Cut Line= 3
      2845124.03      10222360.6      2845109.47     10221951.89
      2844996.43     10221831.24
#Sta/Elev= 30
  4748.7 1103.54  4806.2 1098.87  4816.2  1096.1  4836.2 1092.66    4842 1090.04
    4847  1089.8  4866.3  1086.6  4896.3 1078.39  4916.3 1074.29  4936.3 1068.87
  4946.3 1064.89  4966.3 1052.93  4976.3 1049.21  4993.7 1045.35  4994.1 1044.85
  4998.5 1044.85  4998.9 1045.35  5006.3 1045.43  5016.4 1049.47  5026.4 1052.54
  5036.4 1053.24  5106.4 1056.13  5136.4 1059.26  5160.3 1060.53  5166.7 1061.64
  5187.7 1062.28    5195 1063.49  5223.3 1065.92  5272.7 1067.38    5323 1067.99
#Mann= 3 ,-1 , 0
  4748.7     .12       0  4993.7     .07       0  4998.9     .12       0
Bank Sta=4993.7,4998.9
XS Rating Curve= 0 ,0
Exp/Cntr=0.3,0.1

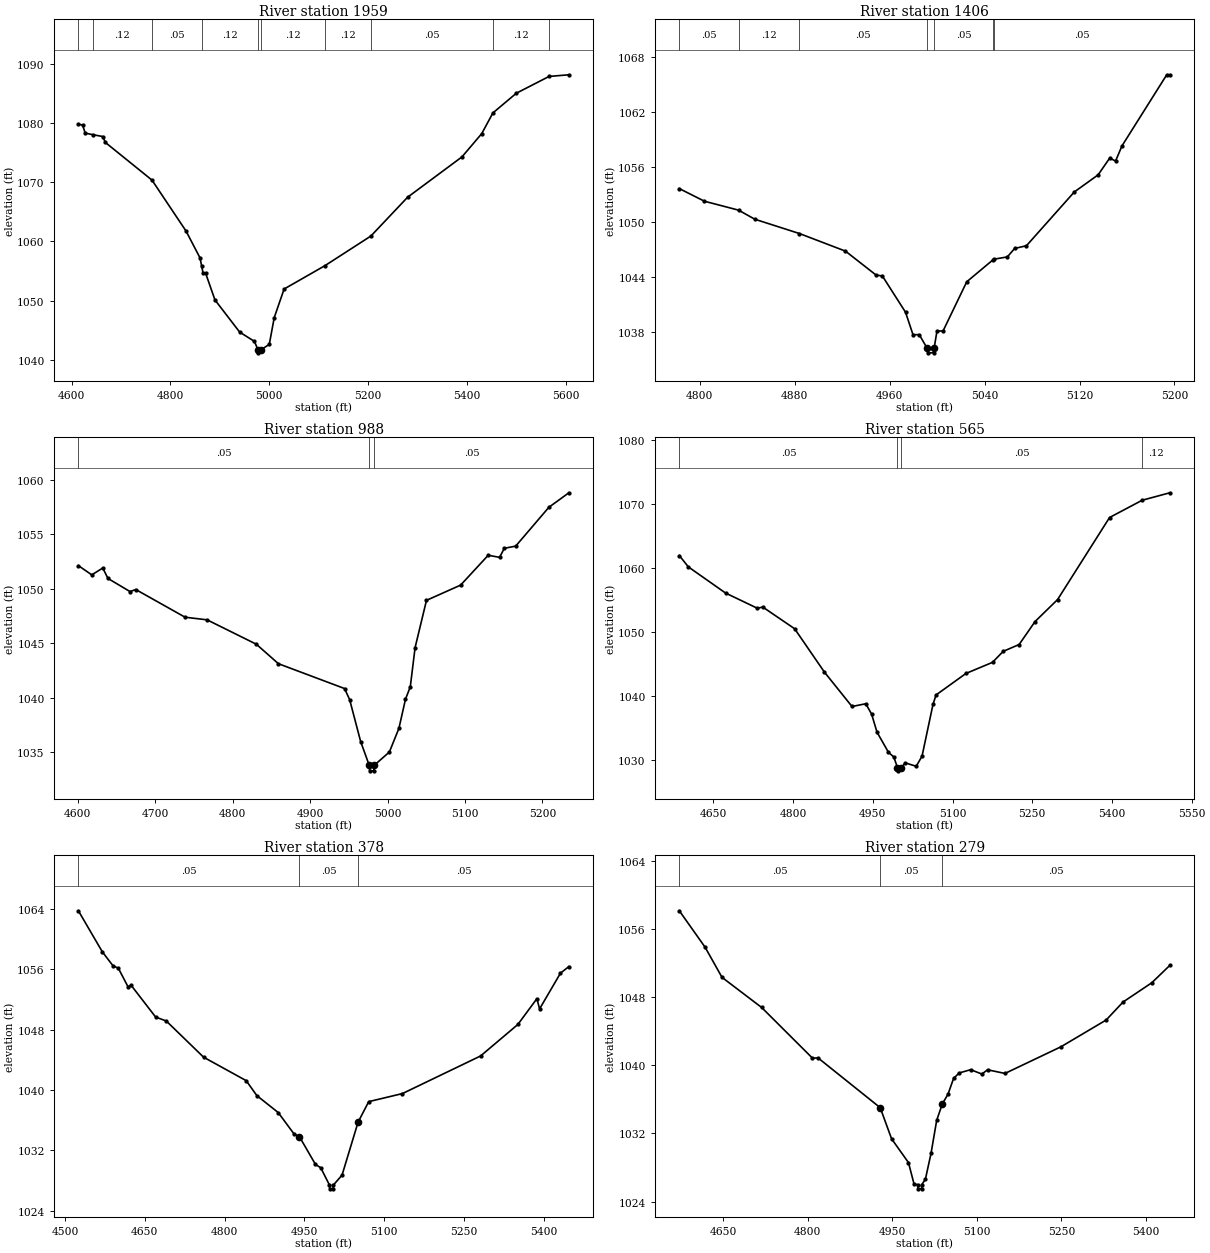
Type RM Length L Ch R = 1 ,1959    ,553,553,553
BEGIN DESCRIPTION:
LITTLE LLANO 010 4.0
END DESCRIPTION:
XS GIS Cut Line= 3
       2845377.3     10222301.58      2845440.13     10222055.95
      2845438.23     10221316.69
#Sta/Elev= 30
  4613.6 1079.82  4622.2 1079.66  4627.4 1078.31  4642.9 1078.04    4663 1077.73
  4668.2 1076.73  4762.6 1070.36  4831.5 1061.75  4859.8 1057.21  4862.9 1055.92
    4866 1054.63  4871.1 1054.63    4890 1050.11    4940 1044.67    4970 1043.09
  4977.1 1041.66  4977.5 1041.16  4982.9 1041.66    5000 1042.59    5010 1047.11
    5030 1051.95  5112.9 1055.91  5205.7 1060.91    5280 1067.47    5390 1074.29
    5430 1078.22  5452.6 1081.72    5500 1085.05  5566.3 1087.89  5606.4 1088.17
#Mann= 10 ,-1 , 0
  4613.6     .05       0  4642.9     .12       0  4762.6     .05       0
  4862.9     .12       0  4977.1     .05       0  4982.9     .12       0
  5112.9     .12       0  5205.7     .05       0  5452.6     .12       0
  5566.3     .05       0
Bank Sta=4977.1,4982.9
XS Rating Curve= 0 ,0
Exp/Cntr=0.3,0.1

Type RM Length L Ch R = 1 ,1406    ,418,418,418
BEGIN DESCRIPTION:
LITTLE LLANO 010 3.0
END DESCRIPTION:
XS GIS Cut Line= 3
      2845905.67     10222203.15        2845977.       10221998.
      2845955.68     10221803.06
#Sta/Elev= 30
  4782.8 1053.67    4804 1052.29  4832.7 1051.32  4846.4 1050.33    4884 1048.77
  4922.8 1046.85  4948.6 1044.24  4953.9 1044.14  4973.4 1040.19  4979.7 1037.74
    4985 1037.74  4991.6 1036.26  4992.1 1035.76    4997 1035.76  4997.5 1036.26
  4999.9 1038.14    5005 1038.14    5025 1043.51  5047.1  1045.9  5048.3 1045.98
  5059.2 1046.22  5065.3 1047.14  5075.3 1047.44  5115.6  1053.3  5135.7 1055.17
  5145.4 1056.99  5150.4 1056.68  5155.8 1058.33  5193.5 1066.08  5196.1 1066.08
#Mann= 7 ,-1 , 0
  4782.8     .05       0  4832.7     .12       0    4884     .05       0
  4991.6     .05       0  4997.5     .05       0  5047.1     .12       0
  5048.3     .05       0
Bank Sta=4991.6,4997.5
XS Rating Curve= 0 ,0
Exp/Cntr=0.3,0.1

Type RM Length L Ch R = 1 ,988     ,423,423,423
BEGIN DESCRIPTION:
LITTLE LLANO 010 2.0
END DESCRIPTION:
XS GIS Cut Line= 3
      2846089.75     10222441.66       2846353.5       10222142.
       2846490.7     10221952.19
#Sta/Elev= 30
  4600.8 1052.14  4618.1 1051.29  4632.3 1051.92    4639 1050.96  4667.4 1049.76
    4675 1049.94  4738.6  1047.4    4767 1047.16  4830.6 1044.92  4859.1 1043.13
  4944.5 1040.85  4951.1 1039.83  4965.3 1035.98  4976.4 1033.79  4976.9 1033.29
  4982.2 1033.29  4982.7 1033.79  5002.4 1035.02  5014.7 1037.19  5023.2 1039.87
  5029.4 1041.01  5035.6 1044.61  5050.3 1048.95  5094.4 1050.35    5130 1053.09
  5144.7  1052.9  5150.8 1053.73  5165.5 1053.93  5208.4  1057.5  5234.2 1058.83
#Mann= 3 ,-1 , 0
  4600.8     .05       0  4976.4     .03       0  4982.7     .05       0
Bank Sta=4976.4,4982.7
XS Rating Curve= 0 ,0
Exp/Cntr=0.3,0.1

Type RM Length L Ch R = 1 ,565     ,187,187,187
BEGIN DESCRIPTION:
Mapping XS 7b60220c
END DESCRIPTION:
XS GIS Cut Line= 4
      2846733.09     10222690.06       2846736.9     10222415.85
      2846660.73     10222187.35      2846681.68     10221779.89
#Sta/Elev= 30
  4585.8 1061.93  4602.8 1060.15  4672.8 1056.06  4732.8 1053.67  4742.8 1053.87
  4802.8 1050.47  4858.9 1043.68  4910.8  1038.3  4936.7 1038.73  4947.7 1037.11
  4957.8 1034.29  4979.4 1031.13  4989.4  1030.4  4996.4 1028.73  4996.9 1028.23
  5003.6 1028.73    5011 1029.48  5031.6 1028.94  5042.6 1030.53  5063.2 1038.63
    5069 1040.11  5125.2 1043.47  5175.2 1045.21  5195.3 1046.93  5225.3    1048
  5255.3  1051.6  5297.6 1055.03  5395.5 1067.88  5456.8 1070.58  5508.9 1071.75
#Mann= 4 ,-1 , 0
  4585.8     .05       0  4996.4     .05       0  5003.6     .05       0
  5456.8     .12       0
Bank Sta=4996.4,5003.6
XS Rating Curve= 0 ,0
Exp/Cntr=0.3,0.1

Type RM Length L Ch R = 1 ,378     ,99,99,99
BEGIN DESCRIPTION:
Mapping XS 7d739be9
END DESCRIPTION:
XS GIS Cut Line= 2
      2846856.86     10222728.18      2846893.02     10221807.29
#Sta/Elev= 30
  4525.2 1063.73  4570.3 1058.28  4590.3 1056.44  4600.3 1056.12    4619 1053.59
    4624 1053.89  4670.4 1049.65  4690.4 1049.13  4760.4 1044.34  4840.5 1041.23
  4860.5 1039.25  4900.6 1037.01  4930.6 1034.15  4940.6  1033.8  4970.6 1030.14
  4980.6 1029.69    4997  1027.4  4997.5  1026.9  5003.8  1026.9  5004.3  1027.4
  5020.6 1028.72  5050.7 1035.73  5070.7 1038.45  5134.1 1039.52  5280.9  1044.5
  5350.9 1048.67  5386.7 1052.09  5391.7 1050.73    5431 1055.47  5446.8 1056.34
#Mann= 3 , 0 , 0
  4525.2     .05       0  4940.6     .05       0  5050.7     .05       0
Bank Sta=4940.6,5050.7
XS Rating Curve= 0 ,0
Exp/Cntr=0.3,0.1

Type RM Length L Ch R = 1 ,279     ,195,195,195
BEGIN DESCRIPTION:
Mapping XS 7f0cdb80
END DESCRIPTION:
XS GIS Cut Line= 3
      2846953.98     10222678.67      2846971.12     10222354.92
      2846992.06     10221810.33
#Sta/Elev= 30
  4572.8 1058.15  4618.4 1053.88  4648.5 1050.33  4718.6  1046.8  4808.7 1040.85
  4818.7 1040.87  4928.8 1035.03  4948.9 1031.38  4978.9 1028.58  4988.9 1026.02
  4995.2    1026  4995.7  1025.5    5002  1025.5  5002.5    1026  5008.9 1026.63
  5018.9 1029.68  5028.9 1033.55  5038.9 1035.48  5048.9 1036.61  5058.9 1038.48
  5068.9 1039.11    5089 1039.49    5109 1038.98    5119 1039.48  5149.9 1039.05
  5249.1 1042.18  5329.1 1045.32  5359.2 1047.44  5410.1  1049.7    5442 1051.74
#Mann= 3 , 0 , 0
  4572.8     .05       0  4928.8     .05       0  5038.9     .05       0
Bank Sta=4928.8,5038.9
XS Rating Curve= 0 ,0
Exp/Cntr=0.3,0.1

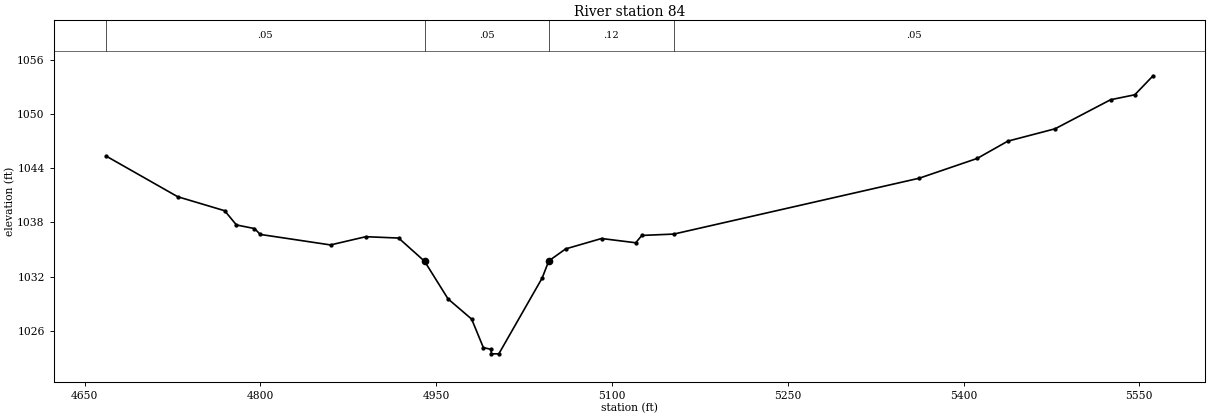
Type RM Length L Ch R = 1 ,84      ,0,0,0
BEGIN DESCRIPTION:
LITTLE LLANO 010 1.0
END DESCRIPTION:
XS GIS Cut Line= 3
      2847140.59     10222613.89      2847172.97     10222208.29
       2847049.2     10221737.99
#Sta/Elev= 30
  4668.5 1045.34  4729.5 1040.85  4769.6  1039.3  4779.6 1037.73    4795 1037.33
    4800 1036.68  4859.9 1035.52    4890 1036.43    4918 1036.28  4940.1 1033.72
  4960.2 1029.55  4980.3 1027.32  4990.3 1024.17  4996.7 1023.98  4997.2 1023.48
  5003.5 1023.48  5040.5 1031.87  5046.1 1033.75  5060.5 1035.08  5091.1 1036.23
  5120.3 1035.76  5125.5 1036.57  5152.8 1036.72  5362.3  1042.9  5411.6 1045.08
  5437.7 1046.99  5478.1 1048.36  5525.4 1051.57  5546.1 1052.12  5561.7 1054.22
#Mann= 4 ,-1 , 0
  4668.5     .05       0  4940.1     .05       0  5046.1     .12       0
  5152.8     .05       0
Bank Sta=4940.1,5046.1
XS Rating Curve= 0 ,0
Exp/Cntr=0.3,0.1

Chan Stop Cuts=-1
Use User Specified Reach Order=0
Composite Channel Slope=5