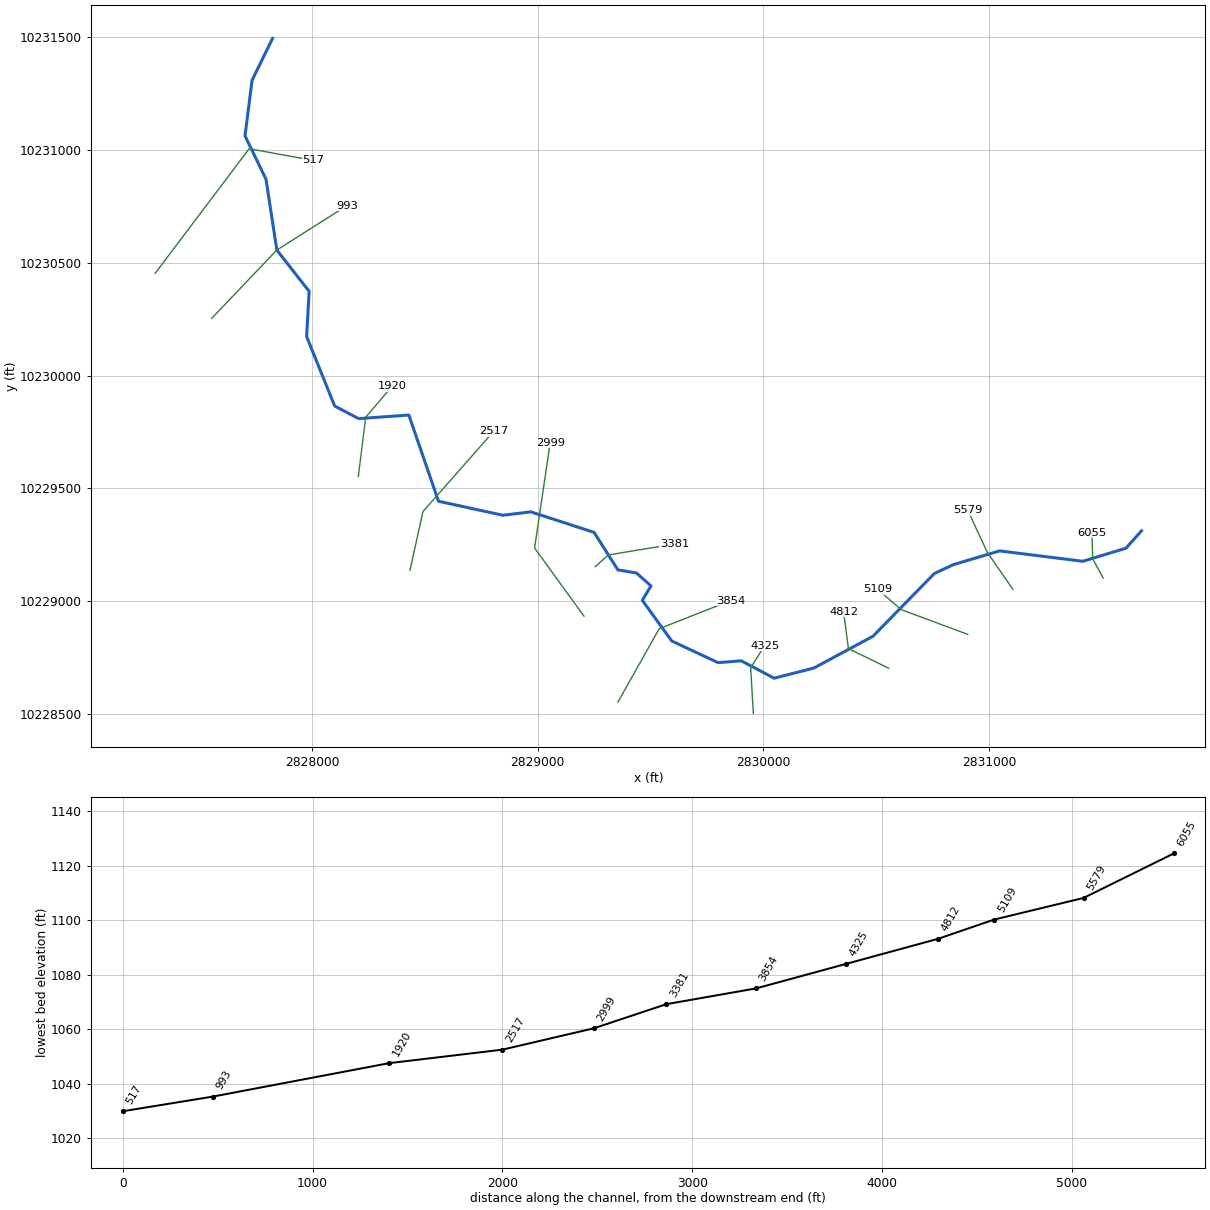
--- LITTLE LLANO 013.prj (project) ---

Proj Title=LITTLE LLANO 013 Base Level Engineering
Current Plan=p01
Default Exp/Contr=0.3,0.1
English Units
Geom File=g01
Flow File=f01
Plan File=p01
BEGIN DESCRIPTION:
LITTLE LLANO 013
END DESCRIPTION:

--- LITTLE LLANO 013.p01 (plan) ---

Plan Title=Multiple Run
Short Identifier=Multiple
Geom File=g01
Flow File=f01
Subcritical Flow
K Sum by GR= 0
Std Step Tol= 0.01
Critical Tol= 0.01
Num of Std Step Trials= 20
Max Error Tol= 0.3
Flow Tol Ratio= 0.001
Split Flow NTrial= 30
Split Flow Tol= 0.02
Split Flow Ratio= 0.02
Log Output Level= 0
Friction Slope Method= 1
Unsteady Friction Slope Method= 2
Unsteady Bridges Friction Slope Method= 1
Parabolic Critical Depth
Global Vel Dist=  1 , 1 , 1
Global Log Level= 0
CheckData=True
Encroach Param= -1, 0, 0, 0
BEGIN DESCRIPTION:
Multiple Run
END DESCRIPTION:

--- LITTLE LLANO 013.f01 (steady flow) ---

Flow Title=Multiple
Number of Profiles=7
Profile Names=10-year,25-year,50-year,1pct_min,100-year,1pct_plu,500-year
River Rch & RM= LITTLE LLANO 013,Reach-1,6055
     107     158     241     210     315     473     452
River Rch & RM= LITTLE LLANO 013,Reach-1,2999
     335     535     783     591    1052    1872    1479
Boundary for River Rch & Prof#=LITTLE LLANO 013,Reach-1,1
Up Type=0
Dn Type=3
Dn Slope=0.005
Boundary for River Rch & Prof#=LITTLE LLANO 013,Reach-1,2
Up Type=0
Dn Type=3
Dn Slope=0.005
Boundary for River Rch & Prof#=LITTLE LLANO 013,Reach-1,3
Up Type=0
Dn Type=3
Dn Slope=0.005
Boundary for River Rch & Prof#=LITTLE LLANO 013,Reach-1,4
Up Type=0
Dn Type=3
Dn Slope=0.005
Boundary for River Rch & Prof#=LITTLE LLANO 013,Reach-1,5
Up Type=0
Dn Type=3
Dn Slope=0.005
Boundary for River Rch & Prof#=LITTLE LLANO 013,Reach-1,6
Up Type=0
Dn Type=3
Dn Slope=0.005
Boundary for River Rch & Prof#=LITTLE LLANO 013,Reach-1,7
Up Type=0
Dn Type=3
Dn Slope=0.005

--- LITTLE LLANO 013.g01 (geometry) ---

Geom Title=Existing Conditions

River Reach=LITTLE LLANO 013,Reach-1
Reach XY= 30
      2831675.50     10229312.00      2831606.75     10229235.00
      2831415.50     10229177.00      2831046.75     10229223.00
      2830841.50     10229162.00      2830758.00     10229123.00
      2830486.00     10228845.00      2830224.00     10228704.00
      2830048.00     10228659.00      2829902.25     10228736.00
      2829799.25     10228728.00      2829594.00     10228824.00
      2829463.75     10229004.00      2829502.25     10229068.00
      2829438.00     10229125.00      2829355.50     10229139.00
      2829250.25     10229305.00      2828970.00     10229396.00
      2828846.00     10229381.00      2828560.75     10229443.00
      2828429.50     10229825.00      2828207.00     10229809.00
      2828100.75     10229865.00      2827976.50     10230173.00
      2827987.75     10230373.00      2827844.50     10230556.00
      2827796.50     10230870.00      2827703.50     10231062.00
      2827734.75     10231308.00      2827825.75     10231494.00

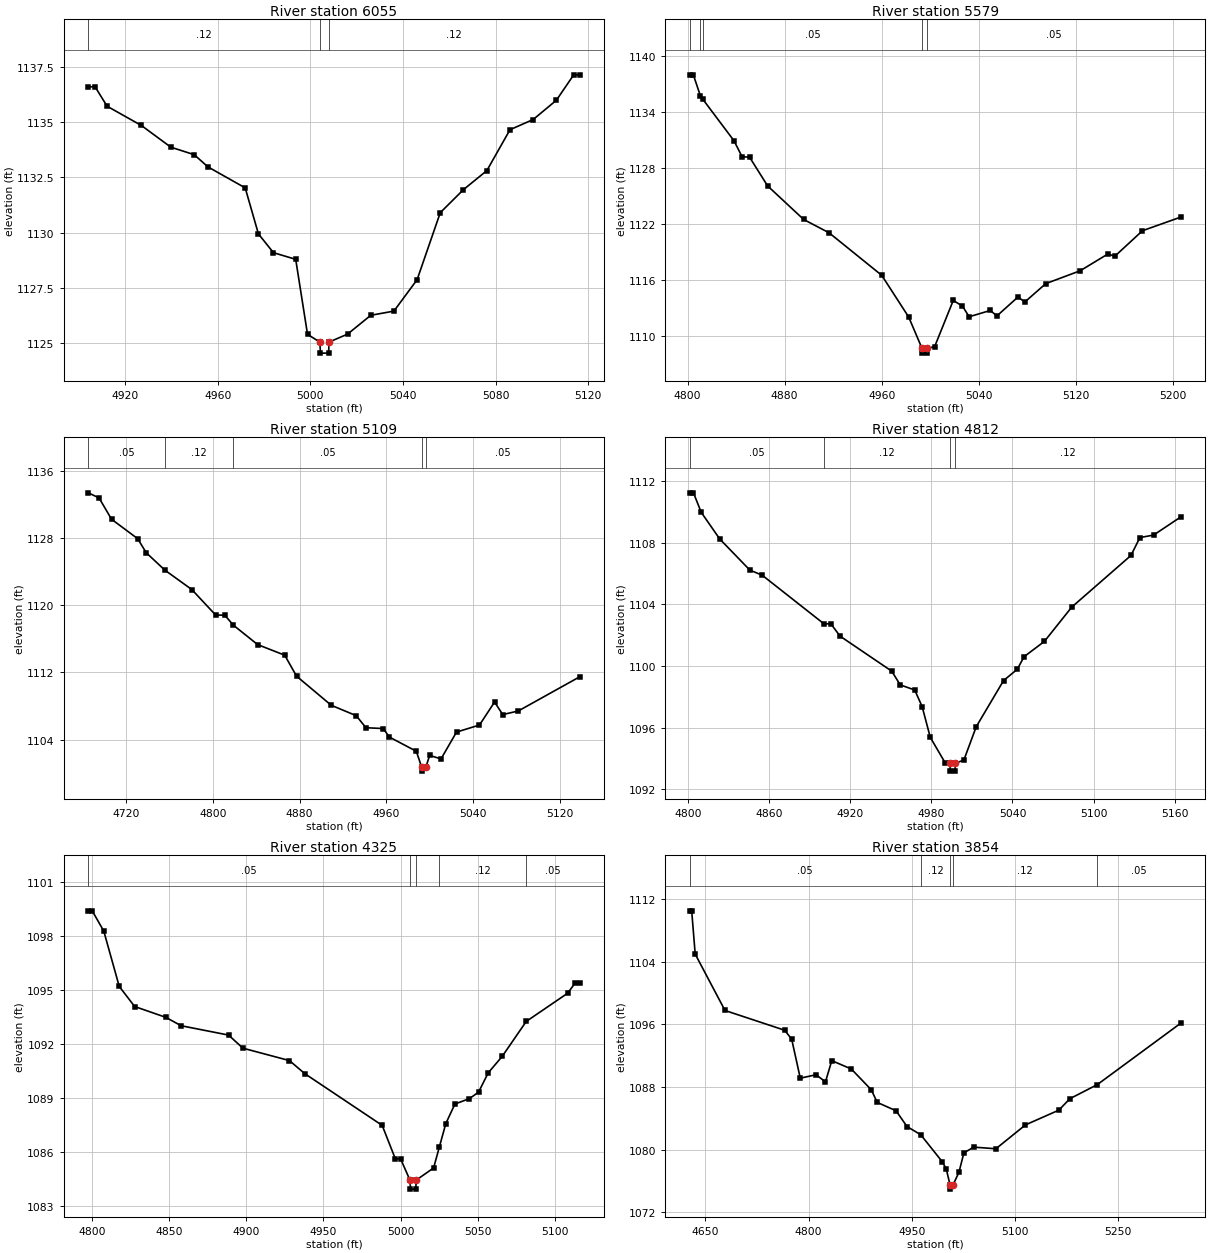
Type RM Length L Ch R = 1,6055,476,476,476
BEGIN DESCRIPTION:
LITTLE LLANO 013 12.0
END DESCRIPTION:
XS GIS Cut Line= 3
      2831505.70     10229103.08      2831459.50     10229187.00
      2831455.68     10229303.14
#Sta/Elev= 28
  4904.2 1136.60  4907.1 1136.60  4912.3 1135.72  4927.1 1134.85  4939.8 1133.87
  4949.9 1133.53  4955.8 1132.98  4971.9 1132.03  4977.6 1129.95  4984.1 1129.10
  4993.7 1128.80  4998.8 1125.41  5004.1 1125.06  5004.4 1124.56  5007.9 1124.56
  5008.1 1125.06  5016.1 1125.42  5026.1 1126.27  5036.1 1126.46  5046.1 1127.88
  5056.1 1130.91  5066.1 1131.95  5076.2 1132.81  5086.2 1134.66  5096.2 1135.12
  5106.2 1135.99  5113.7 1137.14  5116.2 1137.14
#Mann=3,-1,0
  4904.2    0.12       0  5004.1    0.07       0  5008.1    0.12       0
Bank Sta=5004.1,5008.1
Exp/Cntr=0.3,0.1

Type RM Length L Ch R = 1,5579,470,470,470
BEGIN DESCRIPTION:
LITTLE LLANO 013 11.0
END DESCRIPTION:
XS GIS Cut Line= 3
      2831105.68     10229053.12      2830992.75     10229216.00
      2830905.67     10229403.13
#Sta/Elev= 30
  4801.8 1137.96  4804.8 1137.96  4810.7 1135.68  4812.6 1135.35  4838.3 1130.91
  4845.0 1129.19  4851.1 1129.16  4866.0 1126.08  4895.7 1122.49  4916.6 1121.07
  4960.0 1116.52  4982.2 1112.06  4993.2 1108.70  4993.5 1108.20  4997.0 1108.20
  4997.2 1108.70  5003.6 1108.90  5018.9 1113.83  5026.5 1113.23  5032.0 1112.09
  5049.4 1112.76  5054.9 1112.18  5072.3 1114.21  5077.8 1113.66  5095.1 1115.63
  5123.5 1117.01  5146.4 1118.81  5151.9 1118.55  5174.8 1121.29  5206.4 1122.75
#Mann=5,-1,0
  4801.8    0.05       0  4810.7    0.12       0  4812.6    0.05       0
  4993.2    0.03       0  4997.2    0.05       0
Bank Sta=4993.2,4997.2
Exp/Cntr=0.3,0.1

Type RM Length L Ch R = 1,5109,297,297,297
BEGIN DESCRIPTION:
LITTLE LLANO 013 10.0
END DESCRIPTION:
XS GIS Cut Line= 3
      2830905.71     10228853.10      2830610.50     10228963.00
      2830505.70     10229053.09
#Sta/Elev= 30
  4685.0 1133.35  4694.9 1132.74  4706.4 1130.21  4730.5 1127.90  4738.4 1126.23
  4755.5 1124.17  4780.5 1121.85  4802.4 1118.83  4810.9 1118.80  4818.8 1117.62
  4841.2 1115.31  4866.2 1114.05  4877.1 1111.56  4909.1 1108.10  4932.2 1106.86
  4941.1 1105.43  4957.2 1105.33  4962.6 1104.33  4987.6 1102.63  4992.5 1100.77
  4992.7 1100.27  4996.5 1100.77  4999.9 1102.14  5010.4 1101.72  5024.7 1104.91
  5045.9 1105.75  5059.8 1108.48  5067.4 1106.99  5081.7 1107.42  5138.2 1111.47
#Mann=5,-1,0
  4685.0    0.05       0  4755.5    0.12       0  4818.8    0.05       0
  4992.5    0.03       0  4996.5    0.05       0
Bank Sta=4992.5,4996.5
Exp/Cntr=0.3,0.1

Type RM Length L Ch R = 1,4812,487,487,487
BEGIN DESCRIPTION:
LITTLE LLANO 013 9.0
END DESCRIPTION:
XS GIS Cut Line= 3
      2830555.69     10228703.11      2830377.00     10228790.00
      2830355.68     10228953.11
#Sta/Elev= 30
  4801.3 1111.22  4804.1 1111.22  4809.8 1109.96  4823.5 1108.23  4845.8 1106.21
  4854.9 1105.88  4900.7 1102.72  4905.6 1102.74  4912.5 1101.93  4950.7 1099.66
  4957.0 1098.77  4967.7 1098.44  4973.2 1097.36  4979.2 1095.37  4990.2 1093.72
  4993.8 1093.68  4994.0 1093.18  4997.5 1093.18  4997.8 1093.68  5004.1 1093.91
  5013.2 1096.06  5033.4 1099.05  5043.5 1099.78  5048.6 1100.60  5063.6 1101.59
  5083.8 1103.81  5127.6 1107.16  5134.2 1108.32  5144.3 1108.48  5164.5 1109.66
#Mann=4,-1,0
  4801.3    0.05       0  4900.7    0.12       0  4993.8    0.07       0
  4997.8    0.12       0
Bank Sta=4993.8,4997.8
Exp/Cntr=0.3,0.1

Type RM Length L Ch R = 1,4325,471,471,471
BEGIN DESCRIPTION:
LITTLE LLANO 013 8.0
END DESCRIPTION:
XS GIS Cut Line= 3
      2829955.68     10228503.14      2829944.00     10228705.00
      2830005.69     10228803.12
#Sta/Elev= 30
  4797.8 1099.42  4800.3 1099.42  4807.8 1098.29  4817.8 1095.21  4827.8 1094.09
  4847.9 1093.49  4857.9 1093.02  4888.6 1092.50  4897.9 1091.77  4928.0 1091.08
  4938.0 1090.35  4988.1 1087.47  4996.6 1085.61  5000.0 1085.61  5006.1 1084.42
  5006.4 1083.92  5009.9 1083.92  5010.1 1084.42  5021.4 1085.10  5025.2 1086.29
  5029.3 1087.57  5035.2 1088.66  5044.6 1088.96  5050.5 1089.32  5056.8 1090.40
  5065.8 1091.31  5081.4 1093.26  5108.2 1094.83  5112.9 1095.38  5115.9 1095.38
#Mann=5,-1,0
  4797.8    0.05       0  5006.1    0.05       0  5010.1    0.05       0
  5025.2    0.12       0  5081.4    0.05       0
Bank Sta=5006.1,5010.1
Exp/Cntr=0.3,0.1

Type RM Length L Ch R = 1,3854,473,473,473
BEGIN DESCRIPTION:
LITTLE LLANO 013 7.0
END DESCRIPTION:
XS GIS Cut Line= 3
      2829355.68     10228553.10      2829538.50     10228878.00
      2829855.71     10229003.12
#Sta/Elev= 30
  4627.2 1110.50  4630.1 1110.50  4635.2 1104.98  4678.5 1097.78  4765.2 1095.26
  4775.4 1094.13  4787.9 1089.14  4810.8 1089.58  4824.5 1088.67  4833.7 1091.38
  4862.1 1090.31  4891.1 1087.66  4899.7 1086.05  4927.1 1084.98  4943.0 1082.97
  4963.0 1081.92  4994.3 1078.47  5000.0 1077.57  5005.7 1075.48  5006.0 1074.98
  5009.7 1075.48  5018.5 1077.13  5025.7 1079.61  5040.0 1080.34  5072.2 1080.13
  5115.2 1083.18  5163.7 1085.06  5179.7 1086.52  5219.6 1088.32  5341.0 1096.17
#Mann=5,-1,0
  4627.2    0.05       0  4963.0    0.12       0  5005.7    0.07       0
  5009.7    0.12       0  5219.6    0.05       0
Bank Sta=5005.7,5009.7
Exp/Cntr=0.3,0.1

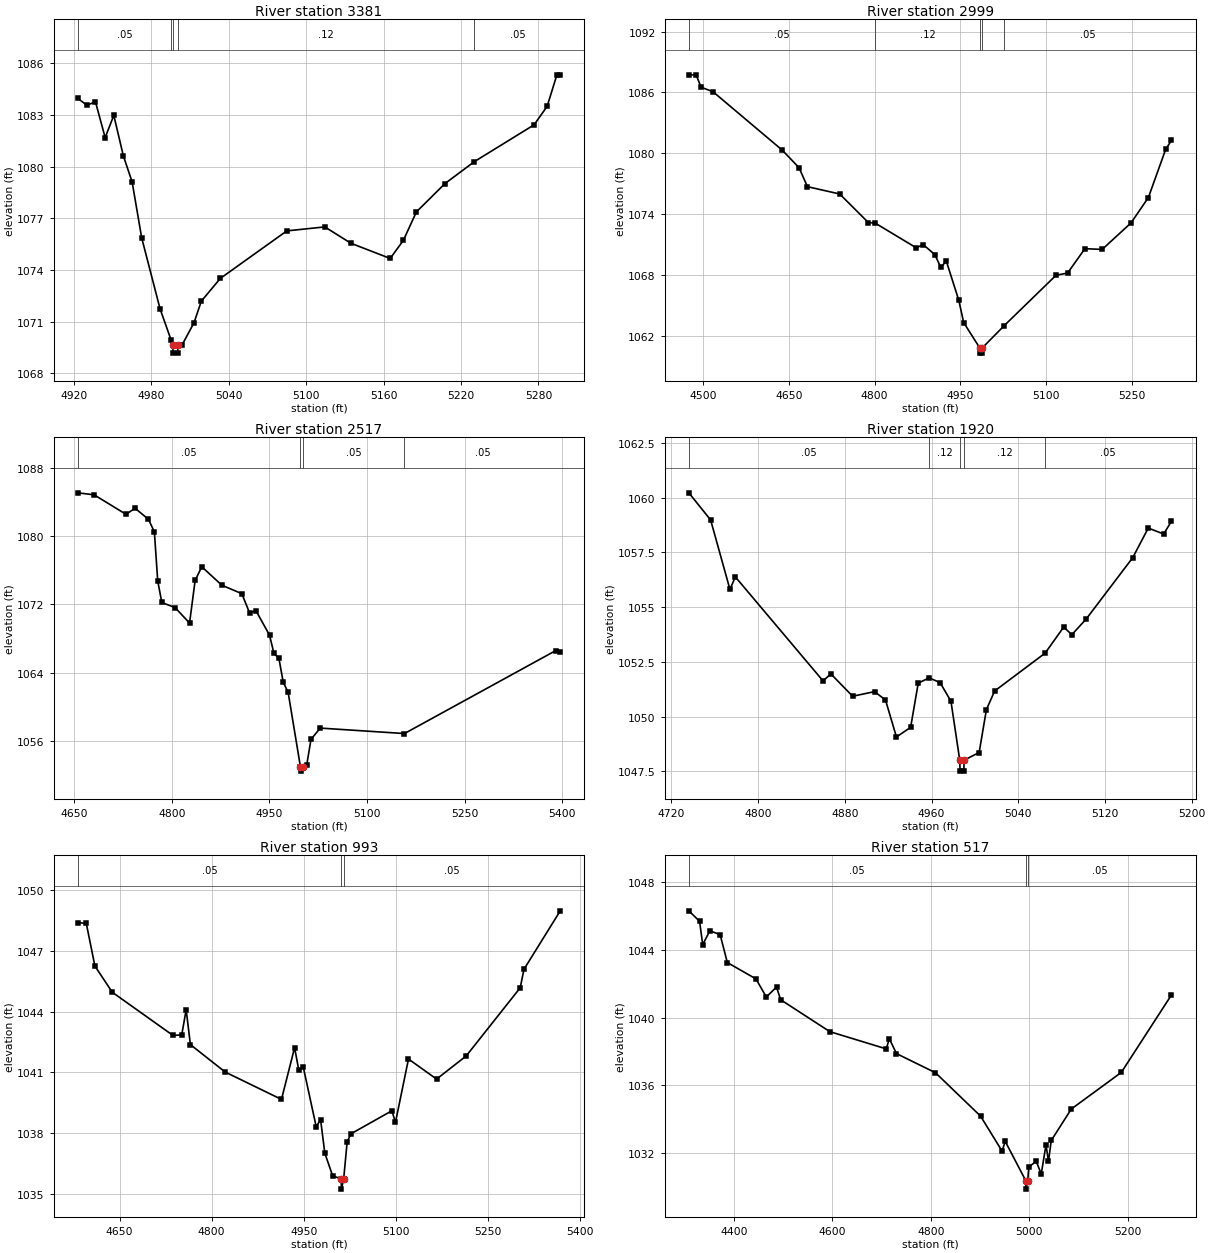
Type RM Length L Ch R = 1,3381,382,382,382
BEGIN DESCRIPTION:
LITTLE LLANO 013 6.0
END DESCRIPTION:
XS GIS Cut Line= 3
      2829255.71     10229153.13      2829312.75     10229205.00
      2829605.72     10229253.12
#Sta/Elev= 30
  4922.9 1083.96  4930.0 1083.56  4936.7 1083.75  4944.2 1081.68  4950.9 1082.97
  4958.3 1080.62  4965.1 1079.11  4972.5 1075.87  4986.7 1071.76  4995.2 1069.96
  4996.6 1069.68  4996.9 1069.18  5000.4 1069.18  5000.6 1069.68  5004.0 1069.68
  5013.1 1070.95  5018.7 1072.19  5033.4 1073.51  5085.0 1076.27  5114.4 1076.50
  5134.7 1075.55  5165.1 1074.67  5175.3 1075.72  5185.4 1077.37  5207.5 1079.01
  5230.4 1080.29  5276.6 1082.42  5286.7 1083.49  5294.3 1085.32  5296.9 1085.32
#Mann=5,-1,0
  4922.9    0.05       0  4995.2    0.12       0  4996.6    0.07       0
  5000.6    0.12       0  5230.4    0.05       0
Bank Sta=4996.6,5000.6
Exp/Cntr=0.3,0.1

Type RM Length L Ch R = 1,2999,482,482,482
BEGIN DESCRIPTION:
LITTLE LLANO 013 5.0
END DESCRIPTION:
XS GIS Cut Line= 3
      2829205.37     10228933.77      2828986.60     10229235.87
      2829055.68     10229703.10
#Sta/Elev= 30
  4474.5 1087.74  4487.3 1087.73  4495.9 1086.52  4516.7 1086.08  4638.1 1080.32
  4667.5 1078.59  4682.2 1076.72  4738.7 1076.00  4789.0 1073.18  4800.6 1073.14
  4872.7 1070.70  4885.1 1071.01  4905.4 1070.02  4915.5 1068.80  4925.6 1069.36
  4947.3 1065.53  4955.9 1063.33  4984.2 1060.82  4984.5 1060.32  4988.0 1060.32
  4988.2 1060.82  5027.1 1063.04  5117.6 1067.99  5137.9 1068.21  5168.2 1070.61
  5198.5 1070.54  5249.0 1073.15  5279.4 1075.65  5309.7 1080.40  5319.8 1081.28
#Mann=5,-1,0
  4474.5    0.05       0  4800.6    0.12       0  4984.2    0.07       0
  4988.2    0.12       0  5027.1    0.05       0
Bank Sta=4984.2,4988.2
Exp/Cntr=0.3,0.1

Type RM Length L Ch R = 1,2517,597,597,597
BEGIN DESCRIPTION:
LITTLE LLANO 013 4.0
END DESCRIPTION:
XS GIS Cut Line= 3
      2828434.52     10229136.93      2828491.81     10229397.33
      2828805.70     10229753.13
#Sta/Elev= 30
  4655.6 1085.06  4680.8 1084.83  4729.7 1082.55  4743.8 1083.25  4764.3 1081.96
  4773.4 1080.48  4778.5 1074.76  4784.8 1072.22  4805.3 1071.61  4827.4 1069.81
  4836.0 1074.81  4846.2 1076.40  4877.0 1074.24  4907.7 1073.25  4919.6 1070.99
  4929.5 1071.24  4950.3 1068.38  4957.0 1066.25  4964.6 1065.69  4971.2 1062.90
  4978.8 1061.69  4997.7 1052.97  4997.9 1052.47  5001.7 1052.97  5007.3 1053.17
  5013.9 1056.19  5028.1 1057.51  5157.4 1056.87  5389.6 1066.58  5396.7 1066.37
#Mann=4,-1,0
  4655.6    0.05       0  4997.7    0.05       0  5001.7    0.05       0
  5157.4    0.05       0
Bank Sta=4997.7,5001.7
Exp/Cntr=0.3,0.1

Type RM Length L Ch R = 1,1920,927,927,927
BEGIN DESCRIPTION:
LITTLE LLANO 013 3.0
END DESCRIPTION:
XS GIS Cut Line= 3
      2828205.68     10229553.12      2828238.25     10229815.00
      2828355.69     10229953.12
#Sta/Elev= 30
  4736.1 1060.22  4756.2 1058.98  4774.0 1055.81  4779.0 1056.38  4859.9 1051.63
  4867.1 1051.95  4887.2 1050.93  4907.4 1051.14  4917.5 1050.76  4927.6 1049.07
  4940.7 1049.51  4947.7 1051.53  4957.8 1051.77  4967.9 1051.55  4977.9 1050.70
  4986.0 1048.01  4986.3 1047.51  4989.8 1047.51  4990.0 1048.01  5003.9 1048.36
  5010.6 1050.32  5018.2 1051.17  5064.8 1052.90  5081.9 1054.09  5089.4 1053.74
  5102.7 1054.46  5145.6 1057.26  5159.9 1058.61  5174.1 1058.34  5181.3 1058.92
#Mann=5,-1,0
  4736.1    0.05       0  4957.8    0.12       0  4986.0    0.07       0
  4990.0    0.12       0  5064.8    0.05       0
Bank Sta=4986,4990
Exp/Cntr=0.3,0.1

Type RM Length L Ch R = 1,993,476,476,476
BEGIN DESCRIPTION:
LITTLE LLANO 013 2.0
END DESCRIPTION:
XS GIS Cut Line= 3
      2827555.70     10230253.12      2827844.50     10230556.00
      2828155.72     10230753.13
#Sta/Elev= 30
  4581.5 1048.37  4595.5 1048.35  4609.6 1046.24  4637.9 1044.95  4737.0 1042.82
  4751.2 1042.85  4758.4 1044.09  4765.3 1042.37  4821.9 1041.02  4913.8 1039.67
  4935.2 1042.22  4942.1 1041.10  4949.3 1041.27  4970.4 1038.33  4977.6 1038.67
  4984.5 1037.02  4997.2 1035.91  5011.2 1035.75  5011.5 1035.25  5015.2 1035.75
  5020.9 1037.57  5026.8 1037.97  5093.8 1039.11  5099.7 1038.54  5120.9 1041.66
  5166.7 1040.67  5215.0 1041.81  5303.1 1045.17  5309.2 1046.08  5368.4 1048.96
#Mann=3,-1,0
  4581.5    0.05       0  5011.2    0.05       0  5015.2    0.05       0
Bank Sta=5011.2,5015.2
Exp/Cntr=0.3,0.1

Type RM Length L Ch R = 1,517,0,0,0
BEGIN DESCRIPTION:
LITTLE LLANO 013 1.0
END DESCRIPTION:
XS GIS Cut Line= 3
      2827305.69     10230453.11      2827722.00     10231005.00
      2828005.69     10230953.11
#Sta/Elev= 30
  4308.7 1046.32  4330.5 1045.70  4336.8 1044.32  4351.4 1045.14  4372.2 1044.91
  4386.8 1043.26  4445.0 1042.29  4465.9 1041.22  4486.7 1041.81  4495.0 1041.06
  4594.9 1039.17  4709.4 1038.15  4715.7 1038.75  4730.2 1037.87  4809.3 1036.74
  4900.9 1034.17  4944.6 1032.10  4950.9 1032.68  4992.6 1030.35  4992.8 1029.85
  4996.6 1030.35  4998.9 1031.17  5013.9 1031.49  5024.1 1030.75  5033.7 1032.47
  5038.8 1031.50  5044.4 1032.73  5085.1 1034.59  5186.7 1036.76  5288.4 1041.34
#Mann=3,-1,0
  4308.7    0.05       0  4992.6    0.05       0  4996.6    0.05       0
Bank Sta=4992.6,4996.6
Exp/Cntr=0.3,0.1

Chan Stop Cuts=-1