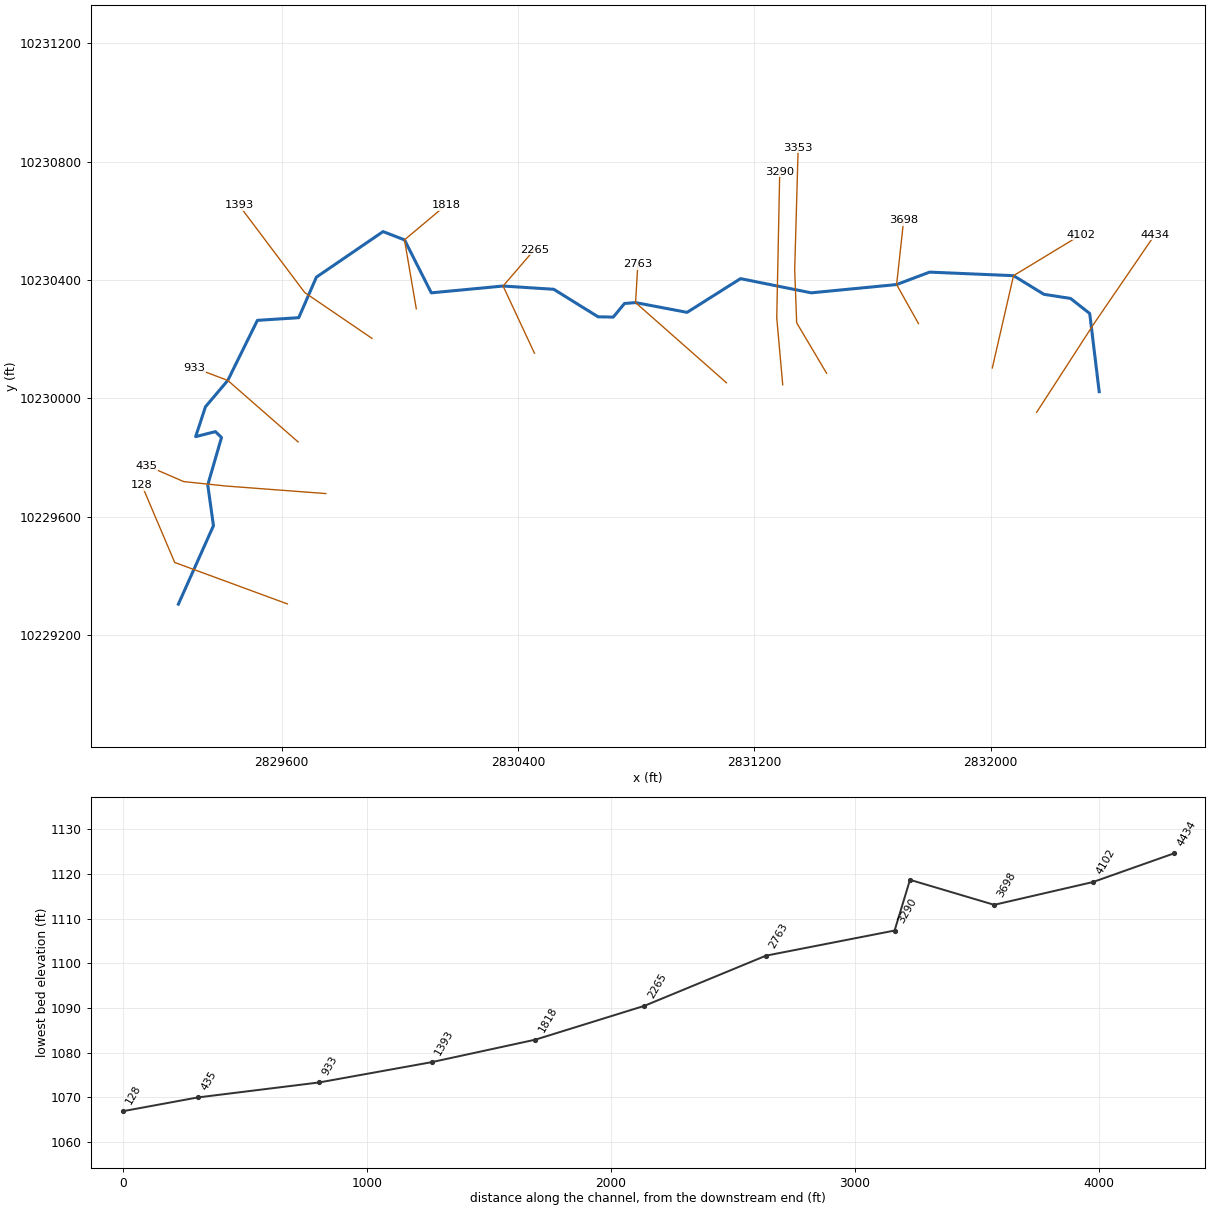
--- LITTLE LLANO 014.prj (project) ---

Proj Title=LITTLE LLANO 014 Base Level Engineering
Current Plan=p01
Default Exp/Contr=0.3,0.1
English Units
Geom File=g01
Flow File=f01
Plan File=p01
Y Axis Title=Elevation
X Axis Title(PF)=Main Channel Distance
X Axis Title(XS)=Station
BEGIN DESCRIPTION:
LITTLE LLANO 014
END DESCRIPTION:
DSS Export Rating Curves= 0
DSS Export Rating Curve Sorted= 0
DSS Export Volume Flow Curves= 0
DXF OffsetX= 0
DXF OffsetY= 0
DXF ScaleX= 1
DXF ScaleY= 10

--- LITTLE LLANO 014.p01 (plan) ---

Plan Title=Multiple Run
Short Identifier=Multiple
Geom File=g01
Flow File=f01
Subcritical Flow
K Sum by GR= 0
Std Step Tol= 0.01
Critical Tol= 0.01
Num of Std Step Trials= 20
Max Error Tol= 0.3
Flow Tol Ratio= 0.001
Split Flow NTrial= 30
Split Flow Tol= 0.02
Split Flow Ratio= 0.02
Log Output Level= 0
Friction Slope Method= 1
Unsteady Friction Slope Method= 2
Unsteady Bridges Friction Slope Method= 1
Parabolic Critical Depth
Global Vel Dist=  1 , 1 , 1
Global Log Level= 0
CheckData=True
Encroach Param= -1, 0, 0, 0
BEGIN DESCRIPTION:
Multiple Run
END DESCRIPTION:

--- LITTLE LLANO 014.f01 (steady flow) ---

Flow Title=Multiple
Number of Profiles=7
Profile Names=10-year,25-year,50-year,1pct_min,100-year,1pct_plu,500-year
River Rch & RM= LITTLE LLANO 014,Reach-1,4434
     189     292     396     308     519     874     730
River Rch & RM= LITTLE LLANO 014,Reach-1,128
     335     535     783     591    1052    1872    1479
Boundary for River Rch & Prof#=LITTLE LLANO 014,Reach-1,1
Up Type=0
Dn Type=3
Dn Slope=0.005
Boundary for River Rch & Prof#=LITTLE LLANO 014,Reach-1,2
Up Type=0
Dn Type=3
Dn Slope=0.005
Boundary for River Rch & Prof#=LITTLE LLANO 014,Reach-1,3
Up Type=0
Dn Type=3
Dn Slope=0.005
Boundary for River Rch & Prof#=LITTLE LLANO 014,Reach-1,4
Up Type=0
Dn Type=3
Dn Slope=0.005
Boundary for River Rch & Prof#=LITTLE LLANO 014,Reach-1,5
Up Type=0
Dn Type=3
Dn Slope=0.005
Boundary for River Rch & Prof#=LITTLE LLANO 014,Reach-1,6
Up Type=0
Dn Type=3
Dn Slope=0.005
Boundary for River Rch & Prof#=LITTLE LLANO 014,Reach-1,7
Up Type=0
Dn Type=3
Dn Slope=0.005

--- LITTLE LLANO 014.g01 (geometry) ---

Geom Title=Existing Conditions
Program Version=4.10

River Reach=LITTLE LLANO 014,Reach-1
Reach XY= 30
       2832367.5       10230023.       2832335.5       10230287.
      2832270.75       10230338.       2832180.5       10230352.
       2832077.5       10230415.      2831793.25       10230427.
      2831681.75       10230385.      2831392.75       10230357.
      2831153.25       10230405.       2830972.5       10230291.
        2830798.       10230324.       2830760.5       10230321.
       2830722.5       10230275.        2830671.       10230276.
        2830521.       10230369.       2830349.5       10230380.
       2830106.5       10230357.      2830015.75       10230536.
      2829943.25       10230564.       2829717.5       10230410.
      2829657.75       10230273.      2829517.75       10230264.
       2829417.5       10230061.        2829342.       10229972.
      2829308.75       10229871.      2829375.75       10229888.
      2829396.25       10229868.      2829349.75       10229708.
        2829369.       10229570.      2829250.25       10229305.

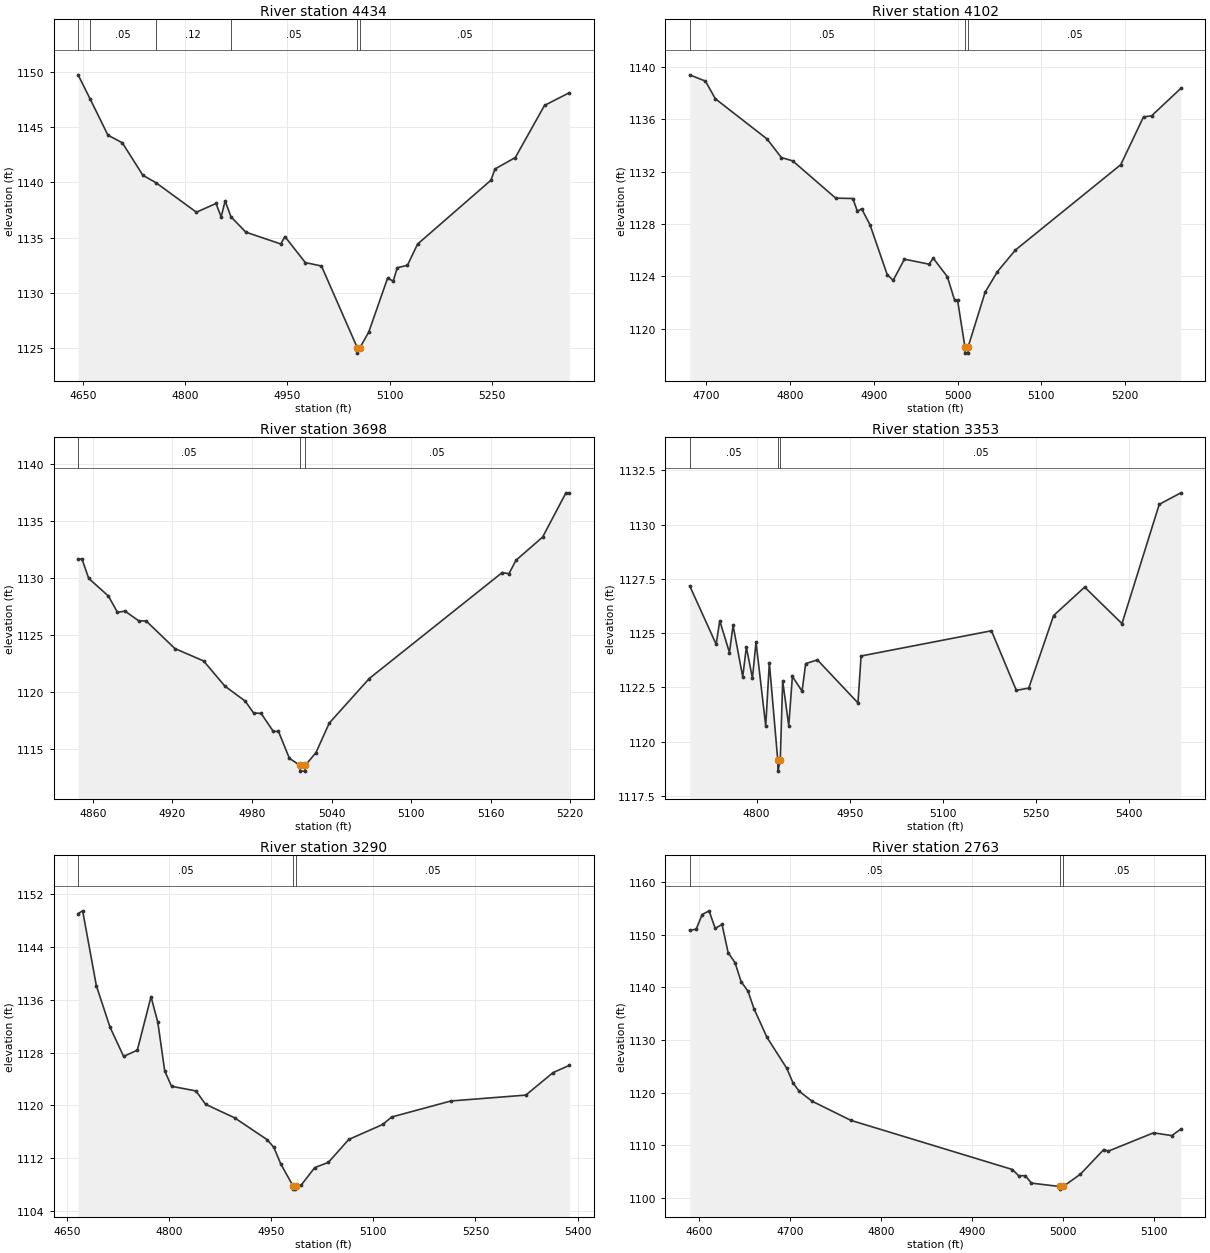
Type RM Length L Ch R = 1 ,4434    ,332,332,332
BEGIN DESCRIPTION:
LITTLE LLANO 014 10.0
END DESCRIPTION:
XS GIS Cut Line= 3
      2832155.71     10229953.14        2832350.       10230253.
      2832555.67     10230553.09
#Sta/Elev= 30
  4642.7  1149.7  4660.7 1147.48  4686.5 1144.25  4707.6 1143.56  4737.9 1140.62
  4756.7 1139.97  4816.4 1137.29  4845.2 1138.08  4852.7 1136.87  4858.6 1138.31
    4867 1136.89  4888.9 1135.49  4940.3 1134.42  4946.3 1135.09  4976.3 1132.74
    5000 1132.43  5052.5 1125.06  5052.7 1124.56  5056.5 1125.06  5069.4 1126.46
  5097.1 1131.34  5105.3 1131.06  5111.3 1132.28  5126.2 1132.49  5141.1 1134.41
  5248.8 1140.18  5254.8  1141.2  5284.6 1142.23  5327.5 1146.94  5363.8 1148.08
#Mann= 6 ,-1 , 0
  4642.7     .12       0  4660.7     .05       0  4756.7     .12       0
    4867     .05       0  5052.5     .05       0  5056.5     .05       0
Bank Sta=5052.5,5056.5
XS Rating Curve= 0 ,0
Exp/Cntr=0.3,0.1

Type RM Length L Ch R = 1 ,4102    ,404,404,404
BEGIN DESCRIPTION:
LITTLE LLANO 014 9.0
END DESCRIPTION:
XS GIS Cut Line= 3
       2832005.7     10230103.16       2832077.5       10230415.
      2832305.66      10230553.1
#Sta/Elev= 30
    4680 1139.39  4698.8 1138.91  4710.7 1137.56  4772.3  1134.5  4789.5 1133.08
  4803.1 1132.82  4854.4 1129.98  4874.9 1129.95  4880.3 1128.98  4885.4 1129.17
  4895.4 1127.94    4916 1124.13  4923.1 1123.71  4936.5 1125.32  4965.9 1124.94
    4971 1125.39  4987.8 1123.98  4996.5 1122.18    5000 1122.18  5008.7 1118.65
    5009 1118.15  5012.5 1118.15  5012.7 1118.65  5032.9  1122.8  5047.6 1124.37
  5068.9 1126.01  5194.9 1132.53  5222.1 1136.18  5231.7 1136.26  5266.7 1138.36
#Mann= 3 ,-1 , 0
    4680     .05       0  5008.7     .05       0  5012.7     .05       0
Bank Sta=5008.7,5012.7
XS Rating Curve= 0 ,0
Exp/Cntr=0.3,0.1

Type RM Length L Ch R = 1 ,3698    ,345,345,345
BEGIN DESCRIPTION:
LITTLE LLANO 014 8.0
END DESCRIPTION:
XS GIS Cut Line= 3
      2831755.69     10230253.11      2831681.75       10230385.
      2831705.68     10230603.09
#Sta/Elev= 30
  4848.8 1131.67  4851.7 1131.67  4856.8 1129.96  4871.7 1128.41  4878.5 1126.98
  4884.2 1127.09  4894.4 1126.25  4900.2 1126.22  4921.8 1123.81  4943.5 1122.72
  4959.5 1120.52  4974.9  1119.2  4981.2 1118.16  4986.9 1118.12  4996.1 1116.54
    5000 1116.54  5008.2 1114.19  5016.2 1113.56  5016.5 1113.06    5020 1113.06
  5020.2 1113.56  5028.3 1114.69  5038.3 1117.27  5068.5 1121.18  5168.8 1130.47
  5173.9 1130.37  5179.2 1131.55  5199.3 1133.58  5216.9 1137.46  5219.4 1137.46
#Mann= 3 ,-1 , 0
  4848.8     .05       0  5016.2     .03       0  5020.2     .05       0
Bank Sta=5016.2,5020.2
XS Rating Curve= 0 ,0
Exp/Cntr=0.3,0.1

Type RM Length L Ch R = 1 ,3353    ,63,63,63
BEGIN DESCRIPTION:
Mapping XS b0876019
END DESCRIPTION:
XS GIS Cut Line= 4
      2831444.66      10230085.3      2831343.43     10230255.69
      2831336.68     10230434.53       2831348.5      10230847.9
#Sta/Elev= 30
  4692.3 1127.18  4734.9 1124.49  4740.7 1125.57  4756.3 1124.11  4762.1 1125.36
  4777.7 1122.99  4783.5 1124.36  4793.3 1122.93  4799.1 1124.59  4814.7 1120.73
  4820.5 1123.64  4834.1 1119.15  4834.4 1118.65  4838.1 1119.15    4842  1122.8
  4851.8 1120.74  4857.6 1123.01  4873.2 1122.33    4879  1123.6  4897.9 1123.77
  4963.2 1121.79  4968.2 1123.95  5178.1 1125.11  5218.1 1122.37  5238.1 1122.47
  5278.1 1125.81  5328.1 1127.12  5388.2 1125.44  5448.2 1130.93    5483 1131.46
#Mann= 3 ,-1 , 0
  4692.3     .05       0  4834.1     .05       0  4838.1     .05       0
Bank Sta=4834.1,4838.1
XS Rating Curve= 0 ,0
Exp/Cntr=0.3,0.1

Type RM Length L Ch R = 1 ,3290    ,527,527,527
BEGIN DESCRIPTION:
LITTLE LLANO 014 7.0
END DESCRIPTION:
XS GIS Cut Line= 3
       2831296.2     10230046.45      2831275.95     10230272.56
      2831286.07     10230766.94
#Sta/Elev= 30
  4666.3 1149.04    4673 1149.46  4693.1 1138.13  4713.1 1131.86  4733.2 1127.41
  4753.3 1128.36  4773.4 1136.46  4783.4 1132.58  4793.5 1125.23  4803.5 1122.89
  4839.4 1122.18  4853.7 1120.15  4896.1 1118.12  4943.9 1114.81  4953.9 1113.63
  4963.9 1111.15  4981.9 1107.81  4982.1 1107.31  4985.6 1107.31  4985.9 1107.81
  4993.9 1107.91  5013.9 1110.57  5033.9 1111.36  5063.9 1114.83  5113.9 1117.11
  5126.8 1118.23  5213.9 1120.66    5324 1121.55    5364 1124.96  5387.8 1126.05
#Mann= 3 ,-1 , 0
  4666.3     .05       0  4981.9     .05       0  4985.9     .05       0
Bank Sta=4981.9,4985.9
XS Rating Curve= 0 ,0
Exp/Cntr=0.3,0.1

Type RM Length L Ch R = 1 ,2763    ,498,498,498
BEGIN DESCRIPTION:
LITTLE LLANO 014 6.0
END DESCRIPTION:
XS GIS Cut Line= 3
      2831105.65     10230053.14        2830798.       10230324.
      2830805.68     10230453.07
#Sta/Elev= 30
  4590.1 1150.84  4597.2 1151.02  4603.8 1153.82  4611.4 1154.52  4618.1 1151.17
  4625.6 1151.95  4632.3 1146.58  4639.9 1144.68  4646.5  1141.1  4654.1 1139.26
  4660.7 1135.94    4675 1130.48  4696.6 1124.65  4703.4 1121.91  4710.1  1120.3
  4724.3  1118.4    4767 1114.75  4944.4 1105.41  4951.1 1104.25  4958.6 1104.23
  4965.3 1102.83  4996.2 1102.19  4996.5 1101.69  5000.2 1102.19  5019.1 1104.54
  5044.7 1109.21  5049.7  1108.9  5099.3 1112.38  5119.3 1111.85  5129.3 1113.09
#Mann= 3 ,-1 , 0
  4590.1     .05       0  4996.2     .03       0  5000.2     .05       0
Bank Sta=4996.2,5000.2
XS Rating Curve= 0 ,0
Exp/Cntr=0.3,0.1

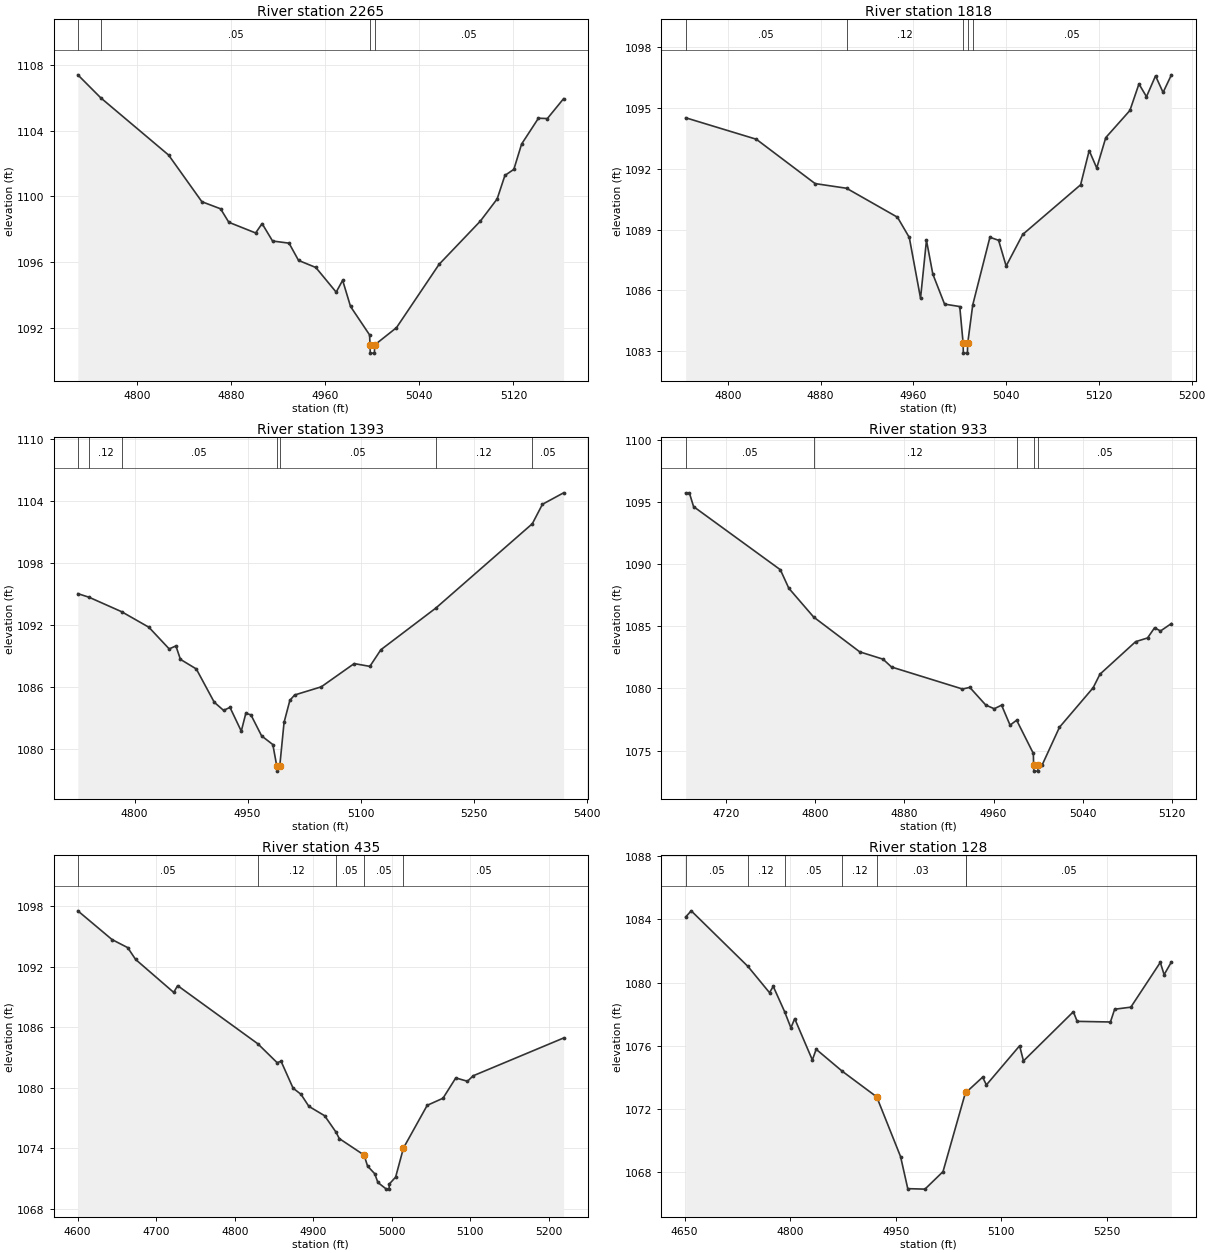
Type RM Length L Ch R = 1 ,2265    ,447,447,447
BEGIN DESCRIPTION:
LITTLE LLANO 014 5.0
END DESCRIPTION:
XS GIS Cut Line= 3
      2830455.68     10230153.12       2830349.5       10230380.
       2830455.7     10230503.13
#Sta/Elev= 30
  4749.5  1107.4    4769    1106  4826.7 1102.52    4855 1099.68  4870.9 1099.25
  4877.9 1098.43  4900.7 1097.78  4906.2 1098.35  4915.1 1097.29  4929.1 1097.16
  4937.2 1096.11  4951.9 1095.68  4969.2 1094.18  4974.7  1094.9  4981.4 1093.31
  4997.6 1091.58    4998 1090.97  4998.2 1090.47  5001.7 1090.47    5002 1090.97
  5020.5 1092.02  5056.7 1095.87  5091.8  1098.5  5106.1 1099.85  5112.7 1101.28
  5120.3 1101.65  5126.9 1103.19  5141.2 1104.76  5148.8 1104.74  5162.6 1105.95
#Mann= 4 ,-1 , 0
  4749.5     .12       0    4769     .05       0    4998     .03       0
    5002     .05       0
Bank Sta=4998,5002
XS Rating Curve= 0 ,0
Exp/Cntr=0.3,0.1

Type RM Length L Ch R = 1 ,1818    ,425,425,425
BEGIN DESCRIPTION:
LITTLE LLANO 014 4.0
END DESCRIPTION:
XS GIS Cut Line= 3
      2830055.69      10230303.1      2830015.75       10230536.
       2830155.7     10230653.13
#Sta/Elev= 30
  4763.7 1094.52  4824.6 1093.46  4875.3 1091.27  4902.4 1091.04  4946.3 1089.61
  4956.5 1088.61  4966.2 1085.61  4971.3 1088.47  4976.8  1086.8  4986.9 1085.32
    5000  1085.2  5002.9  1083.4  5003.1  1082.9  5006.6  1082.9  5006.9  1083.4
  5011.2 1085.28    5026 1088.62  5033.5 1088.47    5040  1087.2  5054.3 1088.76
  5104.2 1091.21  5111.6  1092.9  5118.1 1092.04  5125.9 1093.54  5146.7 1094.88
  5154.5 1096.19    5161 1095.56  5168.8 1096.59  5175.3 1095.77  5182.5 1096.64
#Mann= 5 ,-1 , 0
  4763.7     .05       0  4902.4     .12       0  5002.9     .07       0
  5006.9     .12       0  5011.2     .05       0
Bank Sta=5002.9,5006.9
XS Rating Curve= 0 ,0
Exp/Cntr=0.3,0.1

Type RM Length L Ch R = 1 ,1393    ,460,460,460
BEGIN DESCRIPTION:
LITTLE LLANO 014 3.0
END DESCRIPTION:
XS GIS Cut Line= 3
      2829905.71      10230203.1        2829678.       10230358.
      2829455.67     10230653.13
#Sta/Elev= 30
  4724.6 1095.05  4739.6  1094.7  4782.8  1093.3  4818.9  1091.8  4845.9  1089.7
  4854.8 1089.99  4860.8 1088.69  4881.9 1087.76  4905.7 1084.54  4918.1 1083.75
  4926.6 1084.04  4941.6 1081.74  4947.6 1083.46  4954.4 1083.32  4968.6 1081.28
  4983.5 1080.44  4988.7 1078.37    4989 1077.87  4992.7 1078.37  4998.4 1082.59
  5006.1 1084.72  5012.4 1085.24  5047.8 1086.03  5091.5 1088.28  5112.3 1088.01
  5126.9 1089.62    5200 1093.66    5328 1101.82  5341.4  1103.7  5369.5 1104.81
#Mann= 7 ,-1 , 0
  4724.6     .05       0  4739.6     .12       0  4782.8     .05       0
  4988.7     .05       0  4992.7     .05       0    5200     .12       0
    5328     .05       0
Bank Sta=4988.7,4992.7
XS Rating Curve= 0 ,0
Exp/Cntr=0.3,0.1

Type RM Length L Ch R = 1 ,933     ,498,498,498
BEGIN DESCRIPTION:
LITTLE LLANO 014 2.0
END DESCRIPTION:
XS GIS Cut Line= 3
      2829655.65     10229853.14       2829417.5       10230061.
      2829305.67     10230103.12
#Sta/Elev= 30
  4683.9 1095.74  4687.2 1095.74    4691 1094.63  4768.8 1089.55  4776.4 1088.06
  4798.7 1085.74    4840 1082.94  4860.9 1082.35  4868.5 1081.72  4932.1 1079.95
  4938.7 1080.08    4953 1078.66  4960.6 1078.36  4967.2 1078.65  4974.8 1077.04
  4980.7 1077.44  4995.7 1074.76  4995.9 1073.84  4996.1 1073.34  4999.6 1073.34
  4999.9 1073.84  5003.6 1073.84  5019.1 1076.87  5049.3 1080.05  5055.4 1081.14
  5087.4 1083.76  5098.1 1084.06  5104.4 1084.88  5109.7 1084.62  5119.5 1085.22
#Mann= 5 ,-1 , 0
  4683.9     .05       0  4798.7     .12       0  4980.7     .05       0
  4995.9     .05       0  4999.9     .05       0
Bank Sta=4995.9,4999.9
XS Rating Curve= 0 ,0
Exp/Cntr=0.3,0.1

Type RM Length L Ch R = 1 ,435     ,307,307,307
BEGIN DESCRIPTION:
Mapping XS 1a269b83
END DESCRIPTION:
XS GIS Cut Line= 4
      2829749.05     10229678.68      2829413.32     10229703.99
      2829268.22     10229719.17      2829143.36     10229773.16
#Sta/Elev= 30
  4600.2 1097.51  4643.7 1094.67  4663.7 1093.87  4673.8  1092.7  4722.3 1089.44
  4727.3 1090.11  4829.4 1084.36    4854 1082.49    4859 1082.63  4874.3 1079.97
  4884.4 1079.36  4894.4 1078.17  4914.5 1077.24  4928.7 1075.65  4933.2 1074.98
  4964.7 1073.35 4969.17 1072.26 4978.33  1071.5 4982.29 1070.64  4993.1 1069.98
  4996.6 1069.98  4996.8 1070.48  5004.9 1071.17  5014.9 1074.05  5045.1 1078.27
  5065.2 1078.97  5081.5 1080.98  5096.4 1080.65  5103.6 1081.19  5218.8 1084.93
#Mann= 5 ,-1 , 0
  4600.2     .05       0  4829.4     .12       0  4928.7     .05       0
  4964.7     .05       0  5014.9     .05       0
Bank Sta=4964.7,5014.9
XS Rating Curve= 0 ,0
Exp/Cntr=0.3,0.1

Type RM Length L Ch R = 1 ,128     ,0,0,0
BEGIN DESCRIPTION:
LITTLE LLANO 014 1.0
END DESCRIPTION:
XS GIS Cut Line= 3
      2829619.19      10229305.8      2829237.85     10229445.85
      2829126.49     10229707.38
#Sta/Elev= 30
  4651.4 1084.16  4659.3 1084.55    4740 1081.02  4770.6 1079.36  4775.9 1079.76
  4792.2 1078.14    4801 1077.13  4806.4 1077.71  4831.5 1075.09  4836.9 1075.77
  4873.9 1074.38    4923 1072.75  4956.9 1068.96 4967.12 1066.93 4991.56  1066.9
 5017.21 1068.01  5049.3 1073.05  5049.9 1073.03  5073.5    1074  5078.9 1073.51
  5126.1 1075.99  5131.6 1075.03  5202.5 1078.15  5207.9 1077.54  5255.2  1077.5
  5261.2 1078.31  5284.2 1078.44  5326.1 1081.28  5331.5  1080.5  5341.9 1081.31
#Mann= 7 ,-1 , 0
  4651.4     .05       0    4740     .12       0  4792.2     .05       0
  4873.9     .12       0    4923     .03       0  5049.3     .12       0
  5049.9     .05       0
Bank Sta=4923,5049.3
XS Rating Curve= 0 ,0
Exp/Cntr=0.3,0.1

Chan Stop Cuts=-1
Use User Specified Reach Order=0
Composite Channel Slope=5