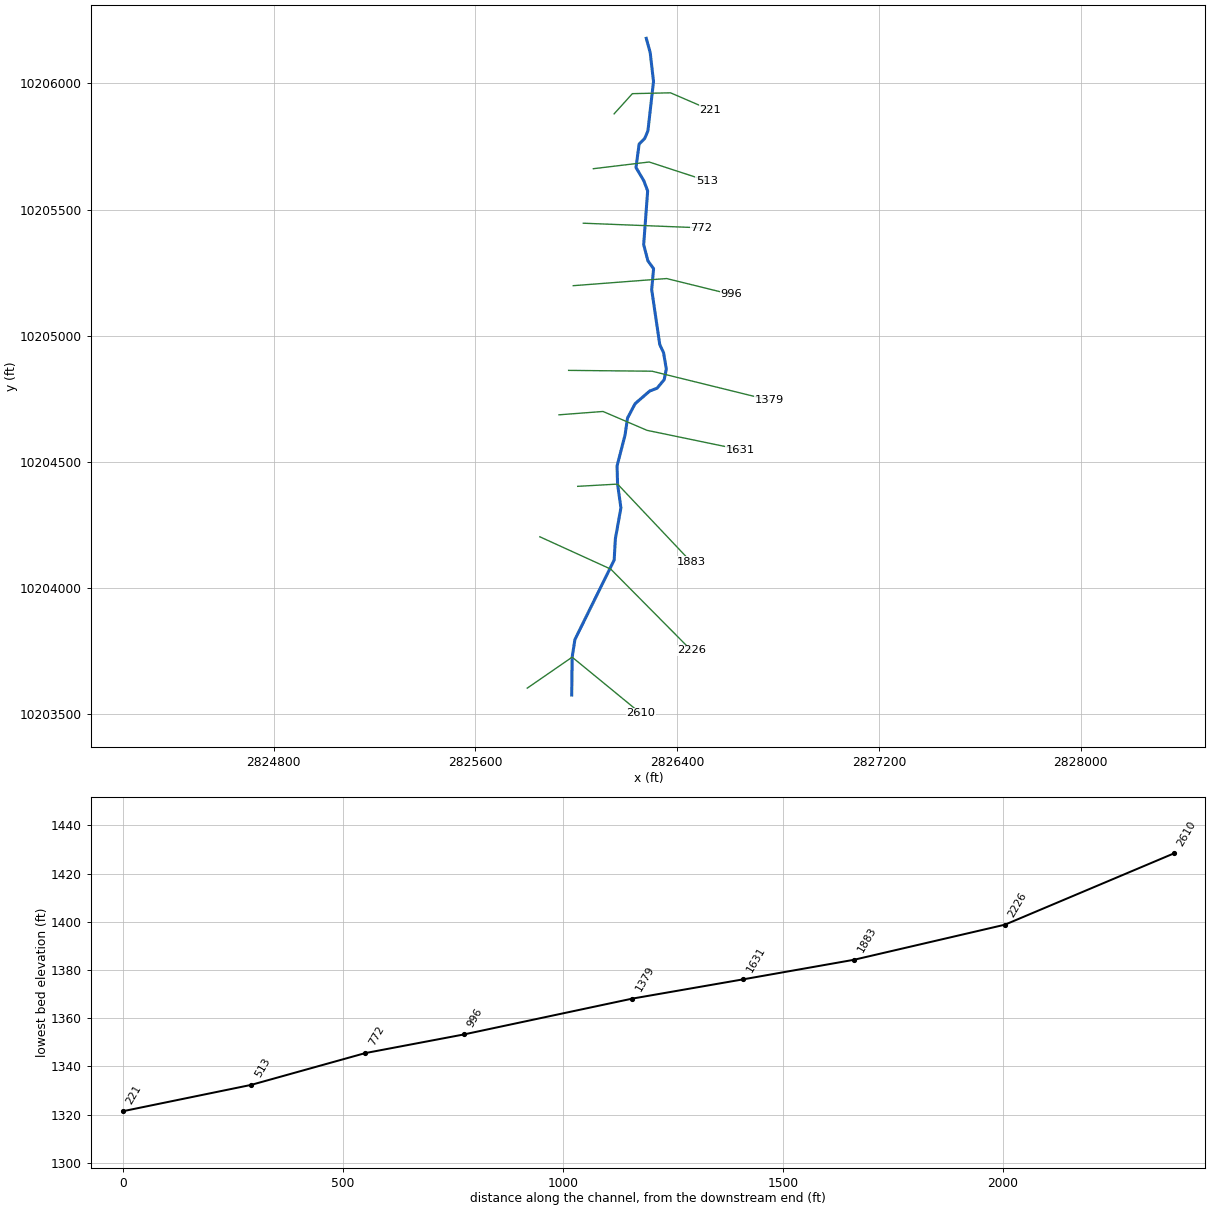
--- LITTLE LLANO 016.prj (project) ---

Proj Title=LITTLE LLANO 016 Base Level Engineering
Current Plan=p01
Default Exp/Contr=0.3,0.1
English Units
Geom File=g01
Flow File=f01
Plan File=p01
BEGIN DESCRIPTION:
LITTLE LLANO 016
END DESCRIPTION:

--- LITTLE LLANO 016.p01 (plan) ---

Plan Title=Multiple Run
Short Identifier=Multiple
Geom File=g01
Flow File=f01
Subcritical Flow
K Sum by GR= 0
Std Step Tol= 0.01
Critical Tol= 0.01
Num of Std Step Trials= 20
Max Error Tol= 0.3
Flow Tol Ratio= 0.001
Split Flow NTrial= 30
Split Flow Tol= 0.02
Split Flow Ratio= 0.02
Log Output Level= 0
Friction Slope Method= 1
Unsteady Friction Slope Method= 2
Unsteady Bridges Friction Slope Method= 1
Parabolic Critical Depth
Global Vel Dist=  1 , 1 , 1
Global Log Level= 0
CheckData=True
Encroach Param= -1, 0, 0, 0
BEGIN DESCRIPTION:
Multiple Run
END DESCRIPTION:

--- LITTLE LLANO 016.f01 (steady flow) ---

Flow Title=Multiple
Number of Profiles=7
Profile Names=10-year,25-year,50-year,1pct_min,100-year,1pct_plu,500-year
River Rch & RM= LITTLE LLANO 016,Reach-1,2610
      75     109     235     222     319     457     484
Boundary for River Rch & Prof#=LITTLE LLANO 016,Reach-1,1
Up Type=0
Dn Type=3
Dn Slope=0.005
Boundary for River Rch & Prof#=LITTLE LLANO 016,Reach-1,2
Up Type=0
Dn Type=3
Dn Slope=0.005
Boundary for River Rch & Prof#=LITTLE LLANO 016,Reach-1,3
Up Type=0
Dn Type=3
Dn Slope=0.005
Boundary for River Rch & Prof#=LITTLE LLANO 016,Reach-1,4
Up Type=0
Dn Type=3
Dn Slope=0.005
Boundary for River Rch & Prof#=LITTLE LLANO 016,Reach-1,5
Up Type=0
Dn Type=3
Dn Slope=0.005
Boundary for River Rch & Prof#=LITTLE LLANO 016,Reach-1,6
Up Type=0
Dn Type=3
Dn Slope=0.005
Boundary for River Rch & Prof#=LITTLE LLANO 016,Reach-1,7
Up Type=0
Dn Type=3
Dn Slope=0.005

--- LITTLE LLANO 016.g01 (geometry) ---

Geom Title=Existing Conditions

River Reach=LITTLE LLANO 016,Reach-1
Reach XY= 30
      2825982.00     10203576.00      2825983.75     10203726.00
      2825994.75     10203796.00      2826150.25     10204111.00
      2826155.00     10204195.00      2826177.00     10204318.00
      2826163.75     10204412.00      2826161.75     10204484.00
      2826193.25     10204606.00      2826203.25     10204674.00
      2826233.50     10204731.00      2826291.25     10204781.00
      2826320.25     10204792.00      2826348.50     10204826.00
      2826357.00     10204868.00      2826346.00     10204933.00
      2826331.00     10204965.00      2826299.00     10205183.00
      2826306.50     10205266.00      2826284.00     10205297.00
      2826267.25     10205361.00      2826283.00     10205574.00
      2826268.00     10205614.00      2826236.75     10205667.00
      2826249.25     10205760.00      2826271.25     10205782.00
      2826284.00     10205812.00      2826306.25     10206008.00
      2826293.00     10206123.00      2826277.50     10206179.00

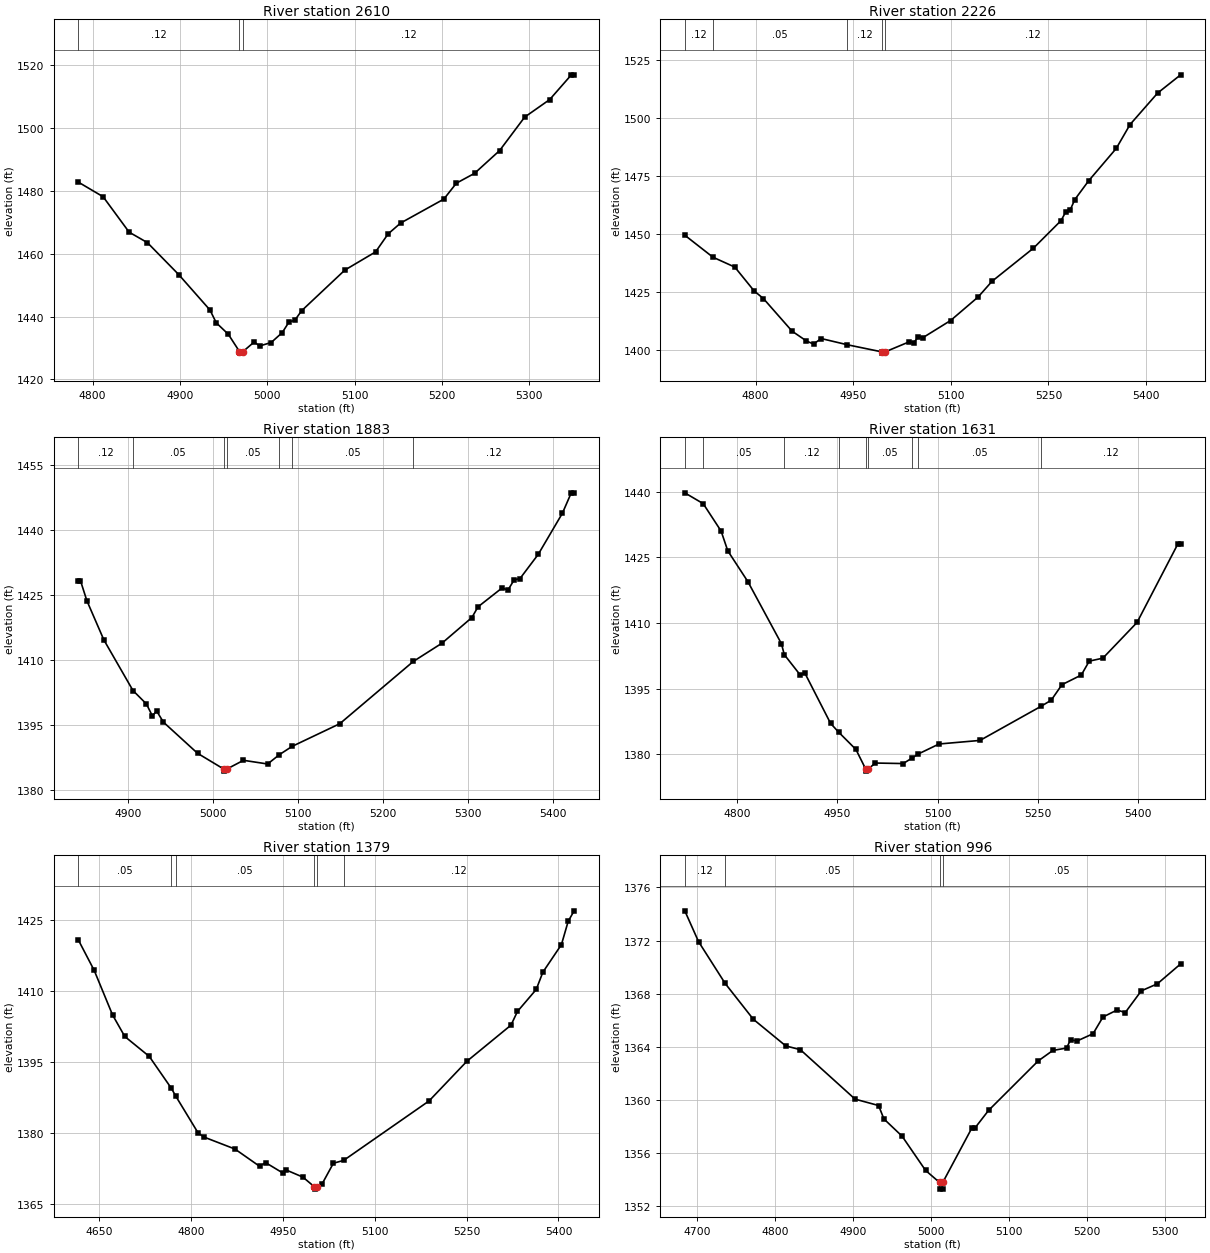
Type RM Length L Ch R = 1,2610,384,384,384
BEGIN DESCRIPTION:
LITTLE LLANO 016 6.0
END DESCRIPTION:
XS GIS Cut Line= 3
      2825805.65     10203603.09      2825983.75     10203726.00
      2826255.68     10203503.12
#Sta/Elev= 30
  4783.6 1482.81  4812.0 1478.16  4841.8 1466.88  4862.7 1463.55  4898.6 1453.37
  4934.4 1442.09  4941.6 1438.02  4955.4 1434.37  4968.2 1428.86  4968.5 1428.36
  4972.2 1428.86  4985.1 1431.92  4991.2 1430.64  5004.5 1431.73  5017.2 1434.90
  5025.1 1438.34  5031.5 1438.79  5039.4 1441.86  5088.9 1454.80  5124.1 1460.59
  5138.5 1466.33  5152.8 1469.78  5202.3 1477.40  5216.7 1482.48  5237.5 1485.61
  5266.2 1492.86  5294.9 1503.51  5323.6 1509.11  5348.4 1516.98  5351.6 1516.98
#Mann=3,-1,0
  4783.6    0.12       0  4968.2    0.07       0  4972.2    0.12       0
Bank Sta=4968.2,4972.2
Exp/Cntr=0.3,0.1

Type RM Length L Ch R = 1,2226,343,343,343
BEGIN DESCRIPTION:
LITTLE LLANO 016 5.0
END DESCRIPTION:
XS GIS Cut Line= 3
      2825855.67     10204203.12      2826136.75     10204075.00
      2826455.66     10203753.14
#Sta/Elev= 30
  4691.1 1449.57  4734.3 1440.12  4768.0 1435.84  4797.6 1425.60  4812.0 1422.27
  4856.0 1408.25  4877.9 1404.06  4888.9 1402.71  4900.7 1405.08  4941.1 1402.39
  4994.7 1399.30  4994.9 1398.80  4998.7 1399.30  5035.9 1403.66  5043.0 1403.36
  5050.1 1405.78  5057.2 1405.49  5099.6 1412.85  5142.0 1423.00  5163.2 1429.72
  5226.9 1444.00  5269.3 1455.86  5276.4 1459.53  5283.5 1460.53  5290.5 1464.94
  5311.7 1472.99  5354.2 1486.96  5375.4 1497.25  5417.8 1510.80  5453.1 1518.64
#Mann=5,-1,0
  4691.1    0.12       0  4734.3    0.05       0  4941.1    0.12       0
  4994.7    0.07       0  4998.7    0.12       0
Bank Sta=4994.7,4998.7
Exp/Cntr=0.3,0.1

Type RM Length L Ch R = 1,1883,252,252,252
BEGIN DESCRIPTION:
LITTLE LLANO 016 4.0
END DESCRIPTION:
XS GIS Cut Line= 3
      2826005.70     10204403.11      2826163.75     10204412.00
      2826455.67     10204103.12
#Sta/Elev= 30
  4841.7 1428.28  4844.2 1428.28  4851.7 1423.66  4871.7 1414.59  4906.0 1402.87
  4921.8 1399.77  4928.8 1397.01  4933.8 1398.15  4941.8 1395.57  4981.9 1388.38
  5012.6 1384.75  5012.9 1384.25  5016.6 1384.75  5036.0 1386.75  5064.4 1385.90
  5078.3 1388.07  5093.3 1389.98  5149.3 1395.21  5235.7 1409.59  5269.5 1413.82
  5304.7 1419.75  5311.9 1422.22  5340.3 1426.60  5347.1 1426.08  5354.4 1428.46
  5361.3 1428.76  5382.7 1434.34  5411.1 1443.83  5421.6 1448.57  5425.0 1448.57
#Mann=7,-1,0
  4841.7    0.12       0  4906.0    0.05       0  5012.6    0.05       0
  5016.6    0.05       0  5078.3    0.12       0  5093.3    0.05       0
  5235.7    0.12       0
Bank Sta=5012.6,5016.6
Exp/Cntr=0.3,0.1

Type RM Length L Ch R = 1,1631,252,252,252
BEGIN DESCRIPTION:
Mapping XS 5d109c7e
END DESCRIPTION:
XS GIS Cut Line= 4
      2825931.53     10204686.61      2826106.08     10204699.90
      2826280.60     10204625.11      2826649.54     10204548.66
#Sta/Elev= 30
  4721.6 1439.74  4749.1 1437.27  4775.9 1431.00  4785.9 1426.48  4816.0 1419.43
  4866.2 1405.24  4870.4 1402.76  4893.9 1398.18  4901.4 1398.48  4939.7 1387.04
  4951.9 1385.01  4977.6 1381.08  4992.1 1376.63  4992.4 1376.13  4996.1 1376.63
  5006.6 1377.98  5048.3 1377.86  5061.4 1379.11  5070.9 1380.05  5101.9 1382.33
  5163.2 1383.15  5254.3 1390.93  5269.7 1392.34  5285.8 1395.89  5314.7 1398.09
  5326.6 1401.27  5347.0 1401.95  5398.1 1410.11  5458.8 1427.95  5463.3 1427.95
#Mann=9,-1,0
  4721.6    0.12       0  4749.1    0.05       0  4870.4    0.12       0
  4951.9    0.05       0  4992.1    0.05       0  4996.1    0.05       0
  5061.4    0.12       0  5070.9    0.05       0  5254.3    0.12       0
Bank Sta=4992.1,4996.1
Exp/Cntr=0.3,0.1

Type RM Length L Ch R = 1,1379,383,383,383
BEGIN DESCRIPTION:
LITTLE LLANO 016 3.0
END DESCRIPTION:
XS GIS Cut Line= 3
      2825969.75     10204862.78      2826300.54     10204859.46
      2826765.91     10204744.78
#Sta/Elev= 30
  4615.5 1420.79  4641.4 1414.36  4671.4 1404.95  4691.4 1400.39  4731.4 1396.18
  4767.5 1389.44  4774.4 1387.85  4811.4 1379.97  4821.4 1379.11  4871.4 1376.61
  4911.5 1372.98  4921.5 1373.74  4949.2 1371.58  4954.3 1372.23  4982.5 1370.67
  5001.1 1368.64  5001.4 1368.14  5005.1 1368.64  5013.4 1369.15  5032.2 1373.61
  5049.0 1374.21  5188.5 1386.77  5250.3 1395.15  5322.4 1402.79  5333.0 1405.69
  5363.6 1410.32  5374.5 1413.98  5404.8 1419.80  5415.9 1424.75  5425.6 1426.94
#Mann=6,-1,0
  4615.5    0.05       0  4767.5    0.12       0  4774.4    0.05       0
  5001.1    0.05       0  5005.1    0.05       0  5049.0    0.12       0
Bank Sta=5001.1,5005.1
Exp/Cntr=0.3,0.1

Type RM Length L Ch R = 1,996,224,224,224
BEGIN DESCRIPTION:
LITTLE LLANO 016 2.0
END DESCRIPTION:
XS GIS Cut Line= 3
      2825988.09     10205198.52      2826358.26     10205226.83
      2826614.64     10205163.62
#Sta/Elev= 30
  4684.6 1374.24  4702.2 1371.92  4736.3 1368.77  4772.4 1366.07  4814.0 1364.06
  4832.6 1363.78  4902.8 1360.05  4932.9 1359.57  4939.7 1358.56  4963.0 1357.26
  4993.1 1354.68  5011.1 1353.77  5011.4 1353.27  5014.9 1353.27  5015.1 1353.77
  5052.1 1357.84  5055.9 1357.84  5073.8 1359.20  5137.4 1362.93  5156.2 1363.72
  5173.7 1363.90  5178.9 1364.52  5187.1 1364.43  5207.7 1364.98  5220.4 1366.24
  5238.6 1366.77  5248.9 1366.57  5269.5 1368.21  5290.1 1368.74  5319.9 1370.24
#Mann=4,-1,0
  4684.6    0.12       0  4736.3    0.05       0  5011.1    0.05       0
  5015.1    0.05       0
Bank Sta=5011.1,5015.1
Exp/Cntr=0.3,0.1

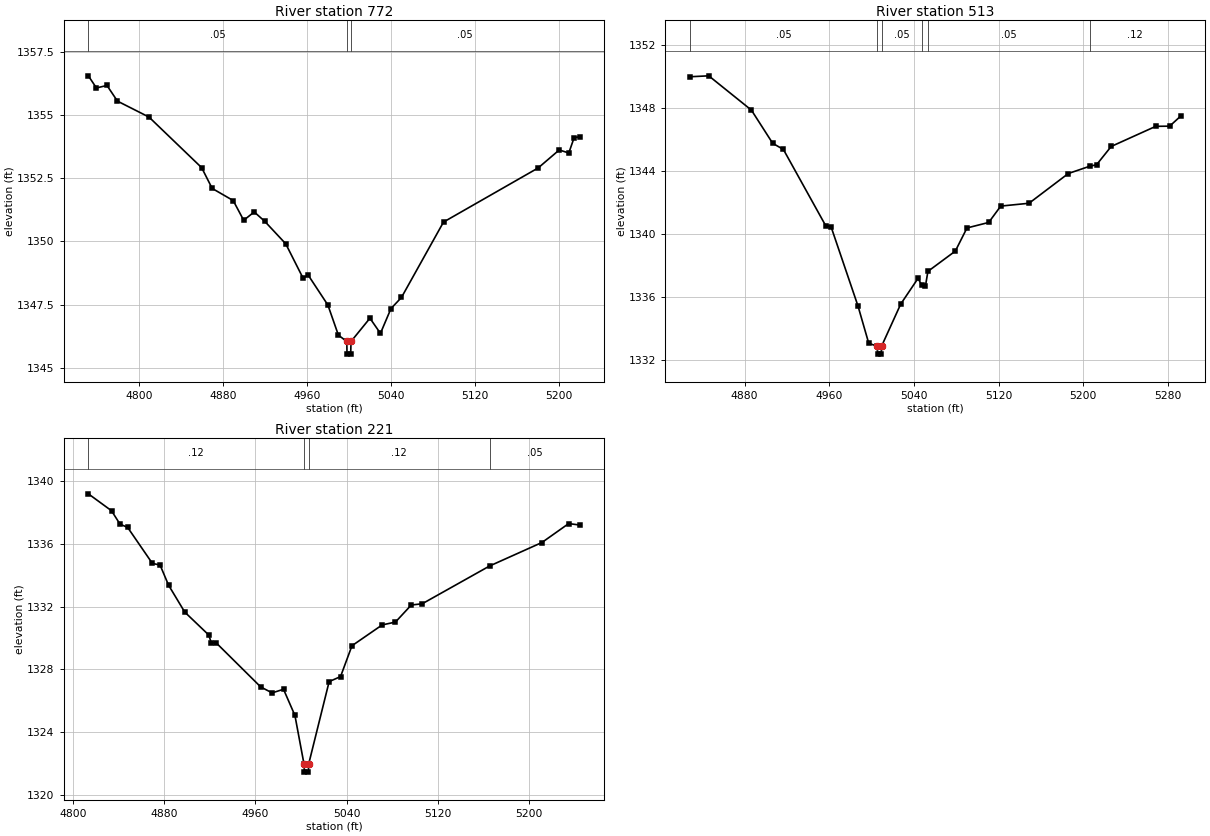
Type RM Length L Ch R = 1,772,259,259,259
BEGIN DESCRIPTION:
Mapping XS 8d7e774a
END DESCRIPTION:
XS GIS Cut Line= 2
      2826028.01     10205446.16      2826494.95     10205427.88
#Sta/Elev= 30
  4752.0 1356.54  4759.7 1356.06  4769.7 1356.16  4779.7 1355.54  4809.7 1354.91
  4859.8 1352.91  4869.8 1352.09  4889.8 1351.61  4899.8 1350.83  4909.8 1351.16
  4919.8 1350.79  4939.8 1349.90  4956.2 1348.55  4961.2 1348.66  4979.9 1347.48
  4989.9 1346.29  4997.9 1346.04  4998.1 1345.54  5001.6 1345.54  5001.9 1346.04
  5019.9 1346.96  5029.9 1346.36  5039.9 1347.34  5049.9 1347.78  5089.9 1350.76
  5180.0 1352.90  5200.0 1353.61  5209.1 1353.49  5214.2 1354.10  5219.3 1354.13
#Mann=3,-1,0
  4752.0    0.05       0  4997.9    0.05       0  5001.9    0.05       0
Bank Sta=4997.9,5001.9
Exp/Cntr=0.3,0.1

Type RM Length L Ch R = 1,513,292,292,292
BEGIN DESCRIPTION:
Mapping XS c5b5d6dc
END DESCRIPTION:
XS GIS Cut Line= 3
      2826067.82     10205662.22      2826288.91     10205688.81
      2826518.24     10205614.03
#Sta/Elev= 30
  4828.2 1350.00  4846.2 1350.06  4886.5 1347.88  4906.6 1345.77  4916.7 1345.38
  4956.6 1340.54  4961.7 1340.47  4987.2 1335.42  4997.3 1333.06  5005.4 1332.87
  5005.6 1332.37  5009.1 1332.37  5009.4 1332.87  5027.5 1335.55  5043.8 1337.18
  5047.2 1336.79  5050.9 1336.71  5053.2 1337.63  5079.1 1338.92  5090.1 1340.39
  5110.6 1340.74  5122.0 1341.78  5148.7 1341.96  5185.8 1343.85  5205.9 1344.31
  5212.5 1344.41  5226.3 1345.57  5268.4 1346.85  5281.5 1346.86  5292.1 1347.51
#Mann=6,-1,0
  4828.2    0.05       0  5005.4    0.05       0  5009.4    0.05       0
  5047.2    0.12       0  5053.2    0.05       0  5205.9    0.12       0
Bank Sta=5005.4,5009.4
Exp/Cntr=0.3,0.1

Type RM Length L Ch R = 1,221,0,0,0
BEGIN DESCRIPTION:
LITTLE LLANO 016 1.0
END DESCRIPTION:
XS GIS Cut Line= 4
      2826150.13     10205879.70      2826222.42     10205959.72
      2826373.67     10205963.05      2826531.11     10205895.10
#Sta/Elev= 30
  4813.5 1339.20  4833.8 1338.12  4841.2 1337.27  4848.0 1337.05  4869.6 1334.76
  4876.4 1334.65  4883.8 1333.37  4898.0 1331.65  4919.0 1330.19  4921.3 1329.69
  4925.5 1329.69  4964.6 1326.87  4974.6 1326.49  4984.6 1326.72  4994.6 1325.05
  5002.6 1321.93  5002.9 1321.43  5006.4 1321.43  5006.6 1321.93  5024.6 1327.21
  5034.6 1327.53  5044.6 1329.50  5071.1 1330.83  5082.7 1331.01  5096.6 1332.10
  5106.2 1332.18  5165.2 1334.59  5211.1 1336.09  5234.6 1337.30  5244.1 1337.21
#Mann=4,-1,0
  4813.5    0.12       0  5002.6    0.07       0  5006.6    0.12       0
  5165.2    0.05       0
Bank Sta=5002.6,5006.6
Exp/Cntr=0.3,0.1

Chan Stop Cuts=-1