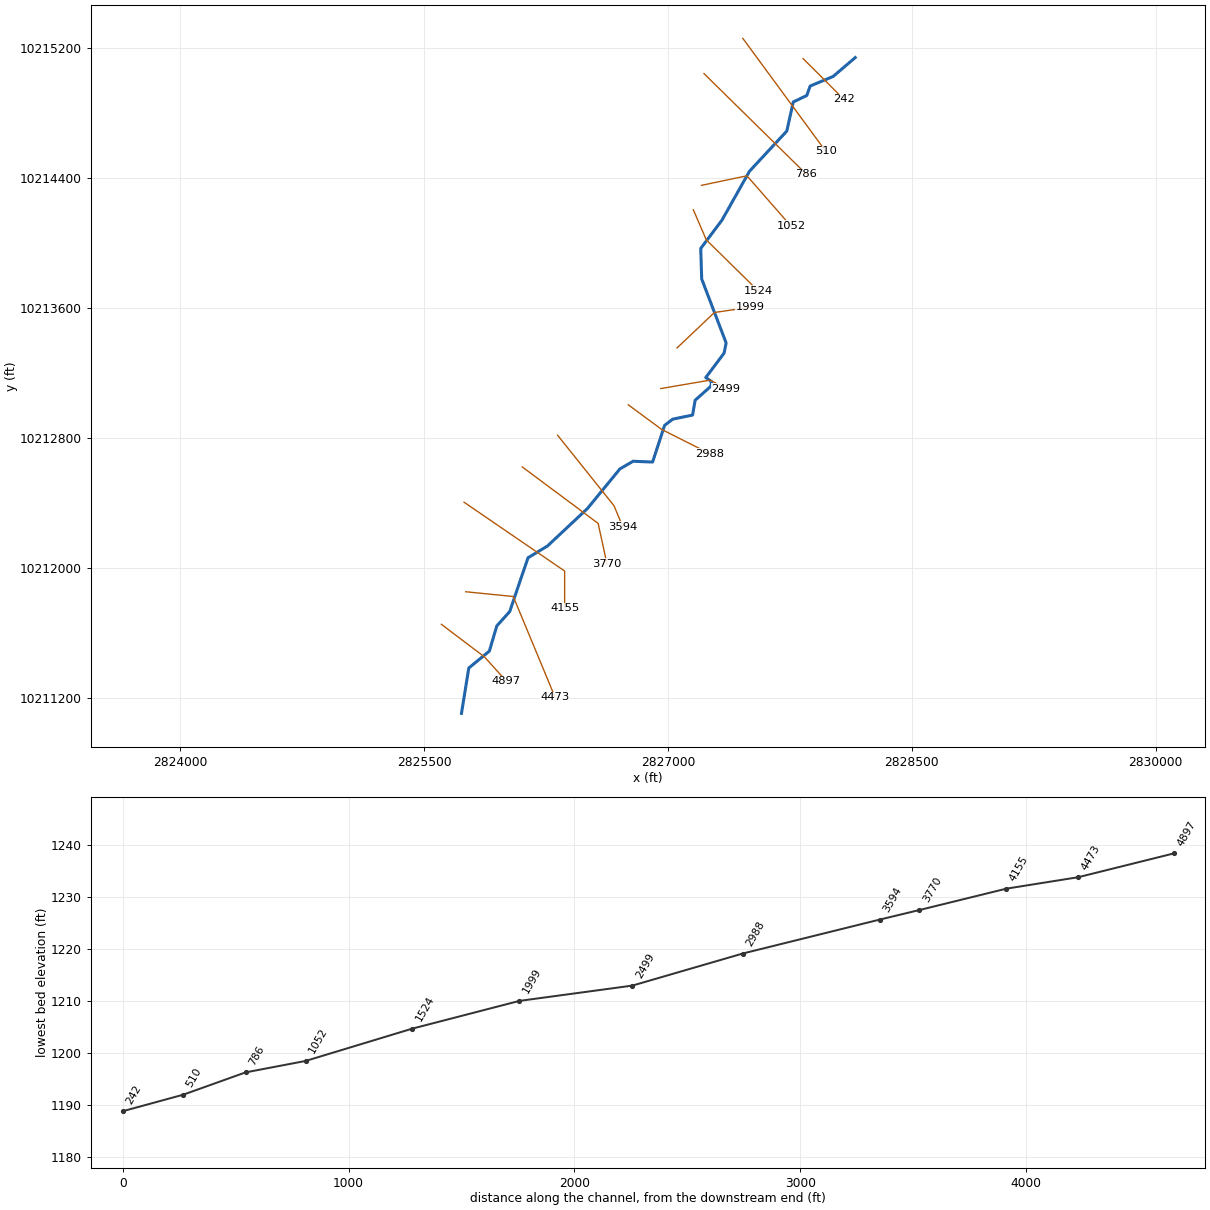
--- LITTLE LLANO 017.prj (project) ---

Proj Title=LITTLE LLANO 017 Base Level Engineering
Current Plan=p01
Default Exp/Contr=0.3,0.1
English Units
Geom File=g01
Flow File=f01
Plan File=p01
BEGIN DESCRIPTION:
LITTLE LLANO 017
END DESCRIPTION:

--- LITTLE LLANO 017.p01 (plan) ---

Plan Title=Multiple Run
Short Identifier=Multiple
Geom File=g01
Flow File=f01
Subcritical Flow
K Sum by GR= 0
Std Step Tol= 0.01
Critical Tol= 0.01
Num of Std Step Trials= 20
Max Error Tol= 0.3
Flow Tol Ratio= 0.001
Split Flow NTrial= 30
Split Flow Tol= 0.02
Split Flow Ratio= 0.02
Log Output Level= 0
Friction Slope Method= 1
Unsteady Friction Slope Method= 2
Unsteady Bridges Friction Slope Method= 1
Parabolic Critical Depth
Global Vel Dist=  1 , 1 , 1
Global Log Level= 0
CheckData=True
Encroach Param= -1, 0, 0, 0
BEGIN DESCRIPTION:
Multiple Run
END DESCRIPTION:

--- LITTLE LLANO 017.f01 (steady flow) ---

Flow Title=Multiple
Number of Profiles=7
Profile Names=10-year,25-year,50-year,1pct_min,100-year,1pct_plu,500-year
River Rch & RM= LITTLE LLANO 017,Reach-1,4897
     148     223     256     205     325     515     446
River Rch & RM= LITTLE LLANO 017,Reach-1,2988
     251     394     469     347     610    1070     840
Boundary for River Rch & Prof#=LITTLE LLANO 017,Reach-1,1
Up Type=0
Dn Type=3
Dn Slope=0.005
Boundary for River Rch & Prof#=LITTLE LLANO 017,Reach-1,2
Up Type=0
Dn Type=3
Dn Slope=0.005
Boundary for River Rch & Prof#=LITTLE LLANO 017,Reach-1,3
Up Type=0
Dn Type=3
Dn Slope=0.005
Boundary for River Rch & Prof#=LITTLE LLANO 017,Reach-1,4
Up Type=0
Dn Type=3
Dn Slope=0.005
Boundary for River Rch & Prof#=LITTLE LLANO 017,Reach-1,5
Up Type=0
Dn Type=3
Dn Slope=0.005
Boundary for River Rch & Prof#=LITTLE LLANO 017,Reach-1,6
Up Type=0
Dn Type=3
Dn Slope=0.005
Boundary for River Rch & Prof#=LITTLE LLANO 017,Reach-1,7
Up Type=0
Dn Type=3
Dn Slope=0.005

--- LITTLE LLANO 017.g01 (geometry) ---

Geom Title=Existing Conditions

River Reach=LITTLE LLANO 017,Reach-1
Reach XY= 30
      2825729.50     10211105.00      2825774.50     10211384.00
      2825901.00     10211488.00      2825946.75     10211643.00
      2826026.00     10211731.00      2826138.75     10212062.00
      2826259.00     10212135.00      2826504.25     10212365.00
      2826704.25     10212609.00      2826785.50     10212656.00
      2826905.00     10212651.00      2826979.25     10212877.00
      2827029.25     10212915.00      2827151.25     10212940.00
      2827166.75     10213031.00      2827263.25     10213117.00
      2827267.00     10213147.00      2827232.50     10213171.00
      2827345.00     10213321.00      2827357.50     10213384.00
      2827207.25     10213777.00      2827201.25     10213965.00
      2827332.50     10214140.00      2827501.25     10214440.00
      2827730.75     10214687.00      2827770.50     10214866.00
      2827853.75     10214906.00      2827874.50     10214964.00
      2828015.75     10215023.00      2828151.75     10215139.00

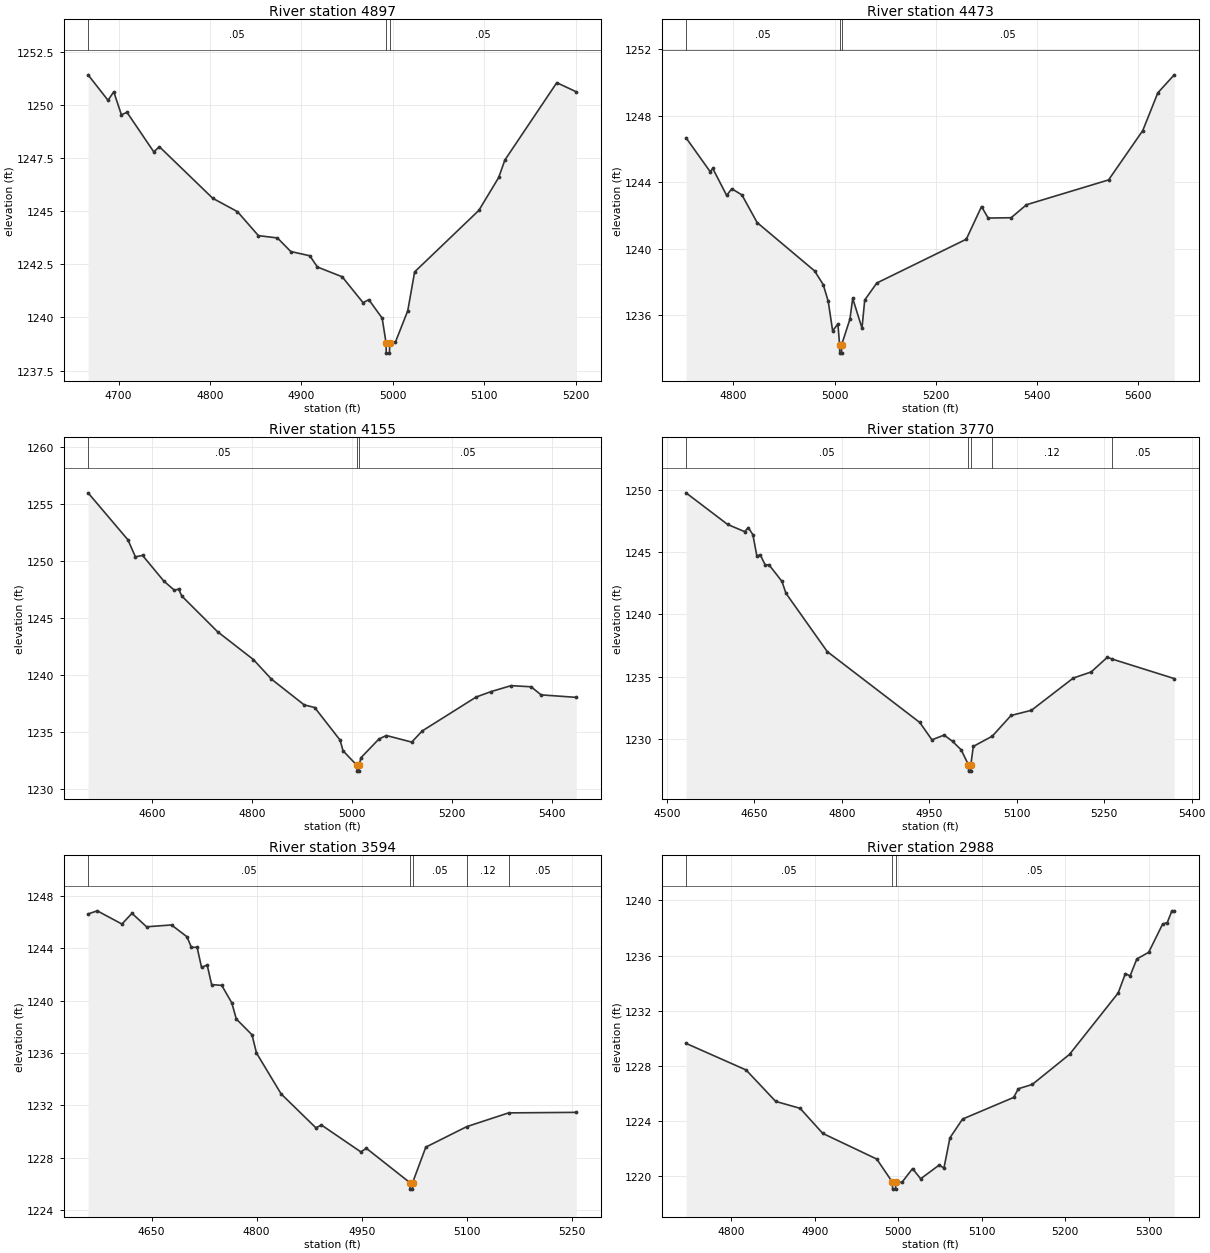
Type RM Length L Ch R = 1,4897,424,424,424
BEGIN DESCRIPTION:
LITTLE LLANO 017 10.0
END DESCRIPTION:
XS GIS Cut Line= 3
      2825605.70     10211653.10      2825871.50     10211452.00
      2826005.66     10211303.14
#Sta/Elev= 30
  4666.7 1251.44  4688.5 1250.24  4694.8 1250.64  4703.1 1249.56  4709.3 1249.67
  4738.5 1247.81  4744.7 1248.05  4803.0 1245.62  4830.0 1244.99  4852.9 1243.86
  4873.7 1243.75  4888.3 1243.11  4909.1 1242.91  4917.4 1242.38  4944.5 1241.92
  4967.3 1240.70  4973.6 1240.84  4988.2 1239.97  4992.4 1238.82  4992.7 1238.32
  4996.2 1238.32  4996.4 1238.82  5002.6 1238.83  5016.2 1240.32  5023.7 1242.15
  5093.9 1245.05  5115.6 1246.60  5122.3 1247.42  5179.1 1251.07  5200.4 1250.64
#Mann=3,-1,0
  4666.7    0.05       0  4992.4    0.05       0  4996.4    0.05       0
Bank Sta=4992.4,4996.4
Exp/Cntr=0.3,0.1

Type RM Length L Ch R = 1,4473,318,318,318
BEGIN DESCRIPTION:
LITTLE LLANO 017 9.0
END DESCRIPTION:
XS GIS Cut Line= 3
      2825755.65     10211853.12      2826048.00     10211824.00
      2826305.67     10211203.15
#Sta/Elev= 30
  4706.2 1246.67  4754.1 1244.63  4759.1 1244.83  4786.6 1243.21  4796.7 1243.61
  4816.8 1243.24  4846.9 1241.58  4960.5 1238.68  4977.6 1237.86  4987.6 1236.85
  4996.3 1235.08  5006.7 1235.49  5010.1 1234.24  5010.4 1233.74  5013.9 1233.74
  5014.1 1234.24  5030.6 1235.79  5036.0 1237.03  5054.4 1235.24  5059.8 1236.93
  5083.7 1237.95  5260.8 1240.58  5290.9 1242.54  5304.1 1241.85  5349.5 1241.87
  5379.9 1242.65  5542.3 1244.14  5609.9 1247.10  5639.8 1249.37  5672.2 1250.45
#Mann=3,-1,0
  4706.2    0.05       0  5010.1    0.05       0  5014.1    0.05       0
Bank Sta=5010.1,5014.1
Exp/Cntr=0.3,0.1

Type RM Length L Ch R = 1,4155,385,385,385
BEGIN DESCRIPTION:
Mapping XS 985bc7e7
END DESCRIPTION:
XS GIS Cut Line= 3
      2825745.67     10212403.78      2826364.16     10211980.61
      2826364.16     10211752.71
#Sta/Elev= 30
  4471.5 1255.99  4551.3 1251.86  4566.2 1250.37  4580.6 1250.49  4623.1 1248.24
  4644.1 1247.44  4652.9 1247.53  4659.0 1246.93  4730.7 1243.79  4802.5 1241.34
  4838.4 1239.63  4904.1 1237.36  4925.1 1237.13  4975.9 1234.27  4981.9 1233.33
  5009.8 1232.04  5010.0 1231.54  5013.5 1231.54  5013.8 1232.04  5017.8 1232.72
  5053.7 1234.36  5068.6 1234.67  5119.4 1234.09  5140.4 1235.07  5248.4 1238.05
  5278.4 1238.53  5318.4 1239.05  5358.4 1238.95  5378.4 1238.24  5448.8 1238.02
#Mann=3,-1,0
  4471.5    0.05       0  5009.8    0.05       0  5013.8    0.05       0
Bank Sta=5009.8,5013.8
Exp/Cntr=0.3,0.1

Type RM Length L Ch R = 1,3770,176,176,176
BEGIN DESCRIPTION:
Mapping XS 6d23377d
END DESCRIPTION:
XS GIS Cut Line= 3
      2826103.75     10212620.80      2826570.33     10212273.58
      2826624.58     10212024.00
#Sta/Elev= 30
  4533.1 1249.74  4604.3 1247.21  4633.5 1246.63  4639.8 1246.95  4647.7 1246.39
  4654.4 1244.71  4660.6 1244.75  4669.0 1243.94  4675.2 1243.98  4697.6 1242.64
  4704.4 1241.69  4775.3 1237.01  4933.9 1231.33  4954.7 1229.94  4975.6 1230.32
  4990.2 1229.81  5004.8 1229.14  5017.4 1227.93  5017.6 1227.43  5021.1 1227.43
  5021.4 1227.93  5025.6 1229.41  5058.1 1230.23  5090.3 1231.89  5125.4 1232.31
  5197.0 1234.89  5227.7 1235.38  5255.5 1236.56  5263.9 1236.41  5370.1 1234.85
#Mann=5,-1,0
  4533.1    0.05       0  5017.4    0.03       0  5021.4    0.05       0
  5058.1    0.12       0  5263.9    0.05       0
Bank Sta=5017.4,5021.4
Exp/Cntr=0.3,0.1

Type RM Length L Ch R = 1,3594,606,606,606
BEGIN DESCRIPTION:
Mapping XS e2fb9e8c
END DESCRIPTION:
XS GIS Cut Line= 3
      2826320.75     10212816.13      2826667.98     10212382.08
      2826722.23     10212251.88
#Sta/Elev= 30
  4559.4 1246.63  4572.5 1246.87  4607.7 1245.86  4622.1 1246.68  4642.9 1245.65
  4678.5 1245.79  4700.5 1244.89  4707.0 1244.07  4715.0 1244.09  4721.4 1242.54
  4729.4 1242.73  4735.8 1241.23  4750.2 1241.17  4764.6 1239.83  4771.0 1238.60
  4793.4 1237.39  4799.8 1236.00  4835.0 1232.87  4884.6 1230.28  4892.6 1230.49
  4948.7 1228.44  4956.7 1228.71  5018.7 1226.09  5019.0 1225.59  5022.5 1225.59
  5022.7 1226.09  5041.5 1228.80  5100.0 1230.37  5159.7 1231.42  5256.3 1231.46
#Mann=5,-1,0
  4559.4    0.05       0  5018.7    0.03       0  5022.7    0.05       0
  5100.0    0.12       0  5159.7    0.05       0
Bank Sta=5018.7,5022.7
Exp/Cntr=0.3,0.1

Type RM Length L Ch R = 1,2988,489,489,489
BEGIN DESCRIPTION:
LITTLE LLANO 017 6.0
END DESCRIPTION:
XS GIS Cut Line= 3
      2826755.71     10213003.10      2826960.50     10212852.00
      2827255.68     10212703.12
#Sta/Elev= 30
  4745.5 1229.64  4817.5 1227.71  4853.0 1225.43  4882.2 1224.93  4909.4 1223.11
  4974.1 1221.25  4992.9 1219.57  4993.1 1219.07  4996.6 1219.07  4996.9 1219.57
  5004.4 1219.57  5017.0 1220.56  5026.7 1219.82  5049.0 1220.82  5054.6 1220.59
  5061.8 1222.79  5076.9 1224.15  5138.2 1225.72  5143.8 1226.35  5160.5 1226.66
  5205.1 1228.84  5263.4 1233.29  5272.1 1234.70  5277.7 1234.53  5285.8 1235.76
  5300.0 1236.24  5316.7 1238.29  5322.3 1238.40  5327.8 1239.25  5330.6 1239.25
#Mann=3,-1,0
  4745.5    0.05       0  4992.9    0.05       0  4996.9    0.05       0
Bank Sta=4992.9,4996.9
Exp/Cntr=0.3,0.1

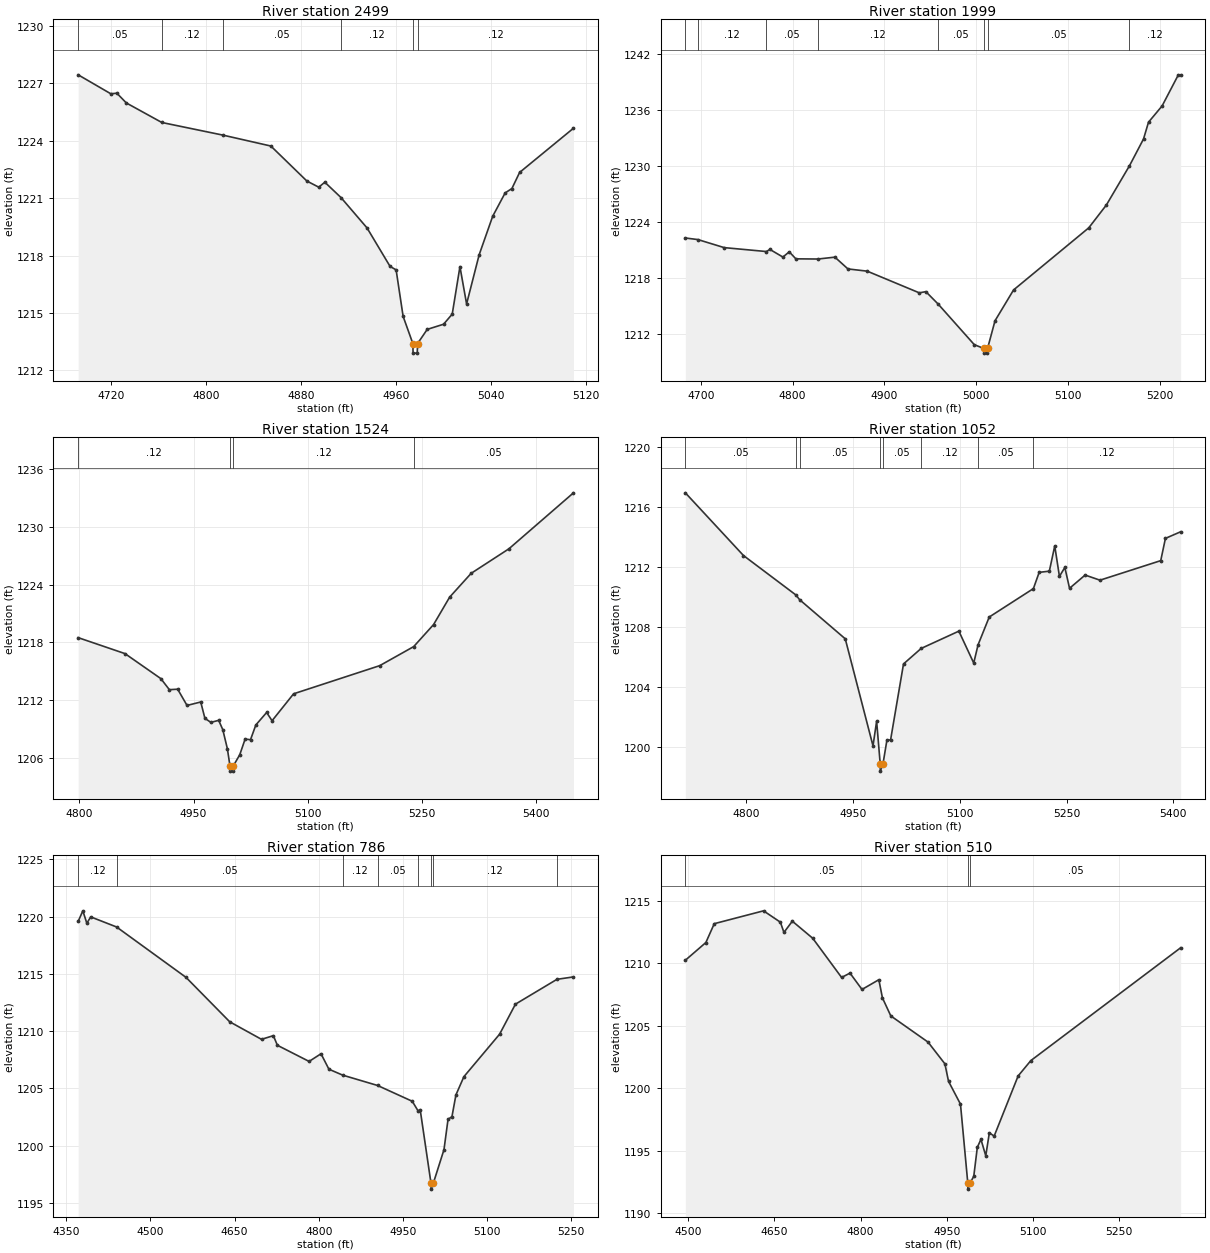
Type RM Length L Ch R = 1,2499,500,500,500
BEGIN DESCRIPTION:
LITTLE LLANO 017 5.0
END DESCRIPTION:
XS GIS Cut Line= 3
      2826955.65     10213103.11      2827259.25     10213155.00
      2827355.68     10213103.12
#Sta/Elev= 30
  4692.0 1227.44  4719.5 1226.45  4724.6 1226.48  4732.6 1225.97  4762.5 1224.95
  4814.0 1224.29  4854.4 1223.72  4884.8 1221.89  4894.8 1221.57  4899.9 1221.83
  4913.5 1221.03  4935.5 1219.44  4954.9 1217.43  4960.0 1217.25  4965.9 1214.82
  4974.1 1213.40  4974.3 1212.90  4977.8 1212.90  4978.1 1213.40  4986.2 1214.14
  5000.0 1214.41  5007.3 1214.94  5013.8 1217.42  5019.4 1215.47  5030.0 1218.04
  5041.4 1220.05  5051.9 1221.27  5057.6 1221.50  5064.1 1222.34  5109.5 1224.65
#Mann=6,-1,0
  4692.0    0.05       0  4762.5    0.12       0  4814.0    0.05       0
  4913.5    0.12       0  4974.1    0.07       0  4978.1    0.12       0
Bank Sta=4974.1,4978.1
Exp/Cntr=0.3,0.1

Type RM Length L Ch R = 1,1999,475,475,475
BEGIN DESCRIPTION:
LITTLE LLANO 017 4.0
END DESCRIPTION:
XS GIS Cut Line= 3
      2827055.67     10213353.10      2827285.50     10213571.00
      2827505.67     10213603.11
#Sta/Elev= 30
  4683.3 1222.28  4697.0 1222.11  4725.6 1221.25  4771.6 1220.83  4775.3 1221.06
  4789.5 1220.24  4796.4 1220.80  4803.6 1220.05  4827.7 1220.03  4846.1 1220.23
  4860.3 1218.97  4881.3 1218.73  4938.0 1216.41  4945.1 1216.54  4958.5 1215.21
  4997.9 1210.86  5008.3 1210.46  5008.5 1209.96  5012.0 1209.96  5012.3 1210.46
  5020.4 1213.42  5040.6 1216.72  5122.5 1223.37  5141.7 1225.82  5166.8 1230.01
  5182.1 1232.88  5187.5 1234.67  5202.3 1236.41  5220.0 1239.74  5222.5 1239.74
#Mann=8,-1,0
  4683.3    0.05       0  4697.0    0.12       0  4771.6    0.05       0
  4827.7    0.12       0  4958.5    0.05       0  5008.3    0.05       0
  5012.3    0.05       0  5166.8    0.12       0
Bank Sta=5008.3,5012.3
Exp/Cntr=0.3,0.1

Type RM Length L Ch R = 1,1524,472,472,472
BEGIN DESCRIPTION:
LITTLE LLANO 017 3.0
END DESCRIPTION:
XS GIS Cut Line= 3
      2827155.68     10214203.12      2827235.50     10214018.00
      2827555.70     10213703.10
#Sta/Elev= 30
  4798.4 1218.50  4859.9 1216.84  4907.0 1214.24  4918.2 1213.09  4929.1 1213.14
  4941.4 1211.45  4959.4 1211.81  4964.9 1210.11  4972.7 1209.69  4983.0 1209.90
  4988.4 1208.93  4994.4 1206.95  4997.9 1205.12  4998.2 1204.62  5001.7 1204.62
  5001.9 1205.12  5010.7 1206.33  5017.7 1207.95  5024.8 1207.89  5031.8 1209.42
  5046.0 1210.72  5053.1 1209.86  5081.4 1212.66  5194.6 1215.59  5239.2 1217.57
  5265.3 1219.86  5286.4 1222.71  5314.7 1225.19  5364.3 1227.74  5449.1 1233.56
#Mann=4,-1,0
  4798.4    0.12       0  4997.9    0.07       0  5001.9    0.12       0
  5239.2    0.05       0
Bank Sta=4997.9,5001.9
Exp/Cntr=0.3,0.1

Type RM Length L Ch R = 1,1052,266,266,266
BEGIN DESCRIPTION:
LITTLE LLANO 017 2.0
END DESCRIPTION:
XS GIS Cut Line= 3
      2827205.73     10214353.12      2827485.50     10214412.00
      2827755.70     10214103.10
#Sta/Elev= 30
  4714.1 1216.92  4795.8 1212.75  4869.4 1210.13  4874.8 1209.81  4938.9 1207.21
  4977.9 1200.09  4983.0 1201.73  4988.0 1198.91  4988.2 1198.41  4992.0 1198.91
  4997.5 1200.48  5002.6 1200.48  5020.8 1205.54  5045.6 1206.57  5098.6 1207.72
  5119.5 1205.60  5125.6 1206.81  5141.3 1208.66  5203.4 1210.55  5211.5 1211.63
  5225.8 1211.71  5233.4 1213.39  5240.0 1211.36  5247.6 1211.96  5254.2 1210.57
  5276.1 1211.45  5297.0 1211.11  5382.4 1212.41  5389.0 1213.89  5410.4 1214.33
#Mann=8,-1,0
  4714.1    0.05       0  4869.4    0.12       0  4874.8    0.05       0
  4988.0    0.05       0  4992.0    0.05       0  5045.6    0.12       0
  5125.6    0.05       0  5203.4    0.12       0
Bank Sta=4988,4992
Exp/Cntr=0.3,0.1

Type RM Length L Ch R = 1,786,276,276,276
BEGIN DESCRIPTION:
Mapping XS ab3b3ee3
END DESCRIPTION:
XS GIS Cut Line= 2
      2827221.35     10215040.53      2827850.70     10214422.02
#Sta/Elev= 30
  4371.4 1219.59  4379.7 1220.51  4386.8 1219.43  4393.8 1219.98  4439.8 1219.10
  4563.5 1214.70  4641.4 1210.82  4698.0 1209.29  4719.1 1209.61  4726.3 1208.77
  4782.8 1207.36  4804.0 1208.03  4818.1 1206.68  4842.8 1206.16  4904.8 1205.26
  4966.6 1203.88  4977.2 1203.02  4980.7 1203.15  5000.0 1196.71  5000.2 1196.21
  5004.0 1196.71  5023.1 1199.66  5030.3 1202.30  5037.3 1202.54  5044.4 1204.44
  5058.6 1206.03  5122.2 1209.74  5150.4 1212.36  5224.4 1214.53  5253.8 1214.74
#Mann=8,-1,0
  4371.4    0.12       0  4439.8    0.05       0  4842.8    0.12       0
  4904.8    0.05       0  4977.2    0.12       0  5000.0    0.07       0
  5004.0    0.12       0  5224.4    0.05       0
Bank Sta=5000,5004
Exp/Cntr=0.3,0.1

Type RM Length L Ch R = 1,510,268,268,268
BEGIN DESCRIPTION:
Mapping XS 29e8c2cc
END DESCRIPTION:
XS GIS Cut Line= 2
      2827460.08     10215257.53      2827970.07     10214563.07
#Sta/Elev= 30
  4495.1 1210.26  4530.8 1211.68  4545.4 1213.19  4631.1 1214.22  4660.4 1213.31
  4666.6 1212.49  4681.2 1213.39  4716.7 1212.02  4766.9 1208.88  4781.5 1209.23
  4802.4 1207.92  4831.7 1208.70  4837.9 1207.25  4852.5 1205.80  4917.3 1203.70
  4946.6 1201.96  4952.9 1200.56  4973.7 1198.73  4986.4 1192.42  4986.6 1191.92
  4990.4 1192.42  4996.8 1192.94  5003.0 1195.27  5009.3 1195.91  5017.7 1194.59
  5023.9 1196.43  5032.3 1196.17  5074.0 1200.99  5096.1 1202.22  5356.7 1211.26
#Mann=3,-1,0
  4495.1    0.05       0  4986.4    0.05       0  4990.4    0.05       0
Bank Sta=4986.4,4990.4
Exp/Cntr=0.3,0.1

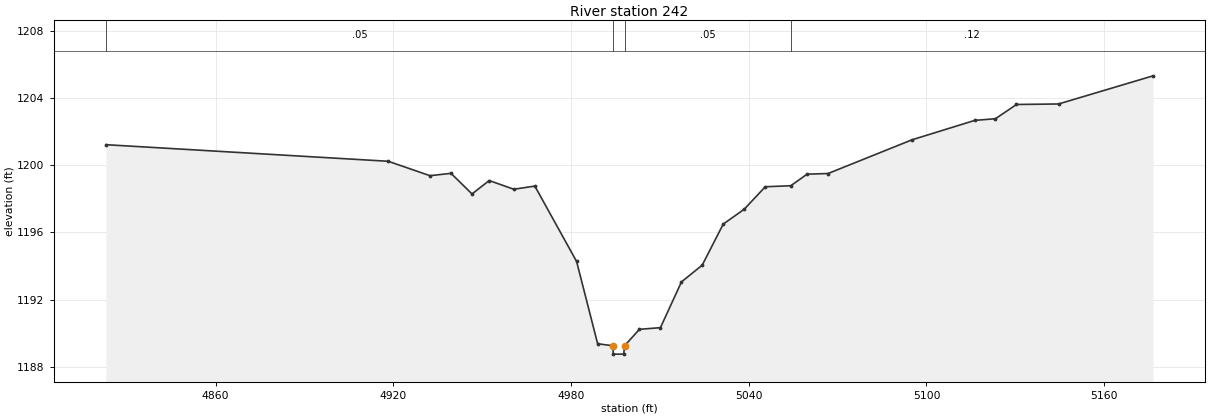
Type RM Length L Ch R = 1,242,0,0,0
BEGIN DESCRIPTION:
LITTLE LLANO 017 1.0
END DESCRIPTION:
XS GIS Cut Line= 3
      2827830.78     10215132.97      2827924.57     10215039.89
      2828080.74     10214883.01
#Sta/Elev= 30
  4823.0 1201.24  4918.3 1200.25  4932.4 1199.39  4939.5 1199.53  4946.6 1198.30
  4952.4 1199.10  4960.7 1198.58  4967.8 1198.77  4981.9 1194.27  4989.0 1189.36
  4994.1 1189.24  4994.3 1188.74  4997.8 1188.74  4998.1 1189.24  5003.1 1190.22
  5010.2 1190.32  5017.3 1193.05  5024.3 1194.05  5031.4 1196.50  5038.5 1197.39
  5045.6 1198.73  5054.2 1198.79  5059.7 1199.48  5066.8 1199.52  5095.1 1201.53
  5116.3 1202.69  5123.3 1202.79  5130.4 1203.64  5144.6 1203.67  5176.5 1205.35
#Mann=4,-1,0
  4823.0    0.05       0  4994.1    0.05       0  4998.1    0.05       0
  5054.2    0.12       0
Bank Sta=4994.1,4998.1
Exp/Cntr=0.3,0.1

Chan Stop Cuts=-1