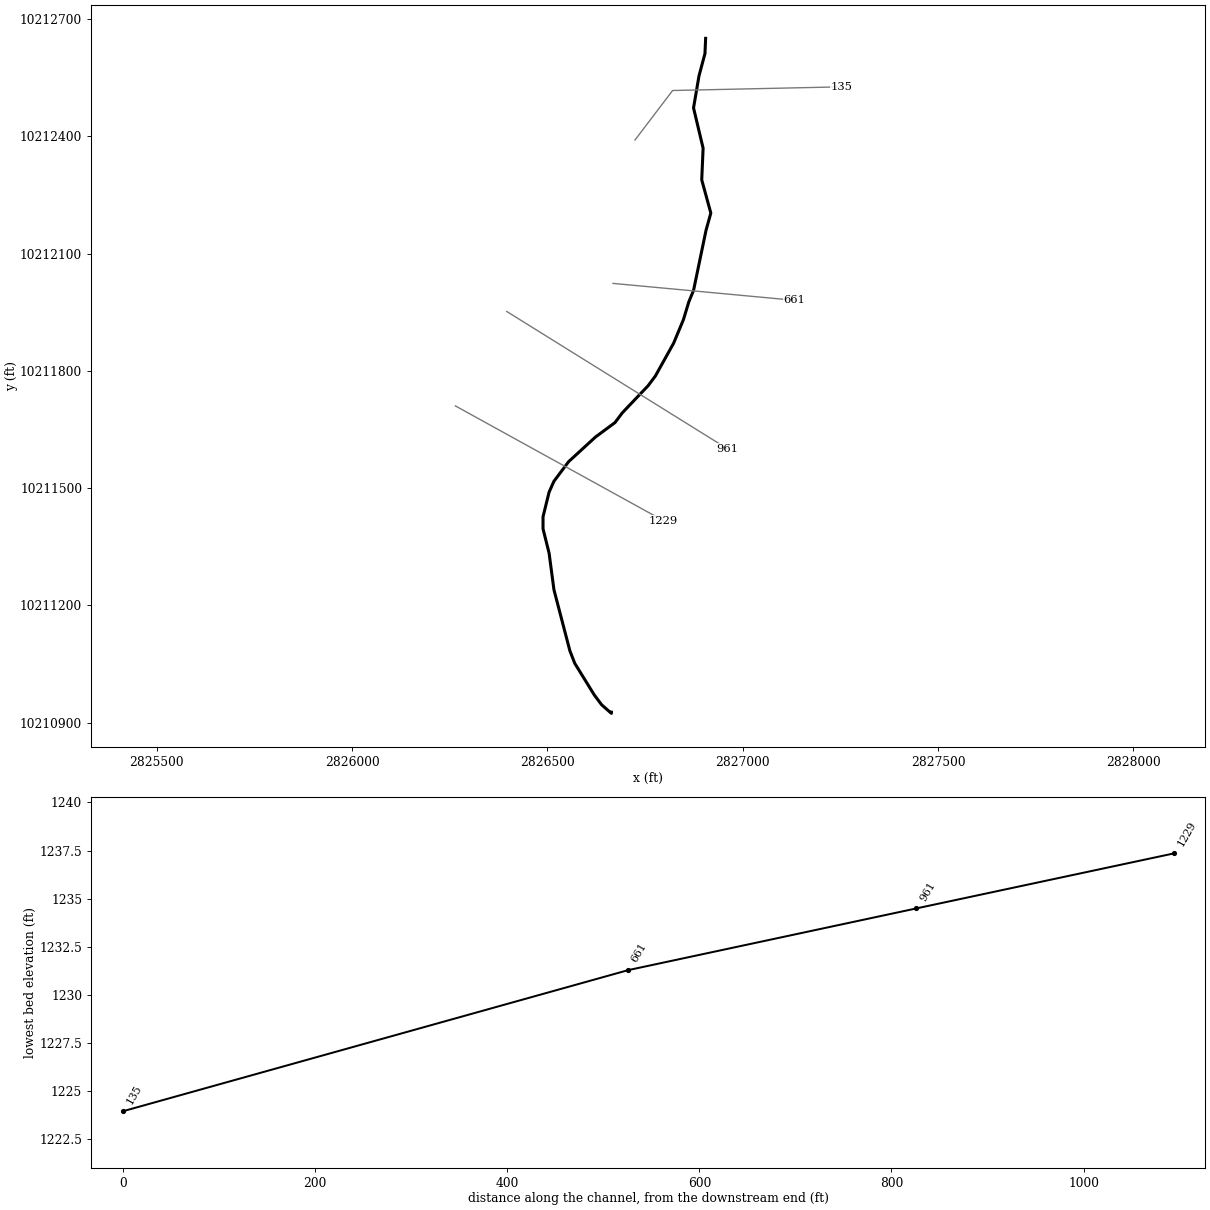
--- LITTLE LLANO 018.prj (project) ---

Proj Title=LITTLE LLANO 018 Base Level Engineering
Current Plan=p01
Default Exp/Contr=0.3,0.1
English Units
Geom File=g01
Flow File=f01
Plan File=p01
BEGIN DESCRIPTION:
LITTLE LLANO 018
END DESCRIPTION:

--- LITTLE LLANO 018.p01 (plan) ---

Plan Title=Multiple Run
Short Identifier=Multiple
Geom File=g01
Flow File=f01
Subcritical Flow
K Sum by GR= 0
Std Step Tol= 0.01
Critical Tol= 0.01
Num of Std Step Trials= 20
Max Error Tol= 0.3
Flow Tol Ratio= 0.001
Split Flow NTrial= 30
Split Flow Tol= 0.02
Split Flow Ratio= 0.02
Log Output Level= 0
Friction Slope Method= 1
Unsteady Friction Slope Method= 2
Unsteady Bridges Friction Slope Method= 1
Parabolic Critical Depth
Global Vel Dist=  1 , 1 , 1
Global Log Level= 0
CheckData=True
Encroach Param= -1, 0, 0, 0
BEGIN DESCRIPTION:
Multiple Run
END DESCRIPTION:

--- LITTLE LLANO 018.f01 (steady flow) ---

Flow Title=Multiple
Number of Profiles=7
Profile Names=10-year,25-year,50-year,1pct_min,100-year,1pct_plu,500-year
River Rch & RM= LITTLE LLANO 018,Reach-1,1229
      55      77      82      76     100     131     137
Boundary for River Rch & Prof#=LITTLE LLANO 018,Reach-1,1
Up Type=0
Dn Type=3
Dn Slope=0.005
Boundary for River Rch & Prof#=LITTLE LLANO 018,Reach-1,2
Up Type=0
Dn Type=3
Dn Slope=0.005
Boundary for River Rch & Prof#=LITTLE LLANO 018,Reach-1,3
Up Type=0
Dn Type=3
Dn Slope=0.005
Boundary for River Rch & Prof#=LITTLE LLANO 018,Reach-1,4
Up Type=0
Dn Type=3
Dn Slope=0.005
Boundary for River Rch & Prof#=LITTLE LLANO 018,Reach-1,5
Up Type=0
Dn Type=3
Dn Slope=0.005
Boundary for River Rch & Prof#=LITTLE LLANO 018,Reach-1,6
Up Type=0
Dn Type=3
Dn Slope=0.005
Boundary for River Rch & Prof#=LITTLE LLANO 018,Reach-1,7
Up Type=0
Dn Type=3
Dn Slope=0.005

--- LITTLE LLANO 018.g01 (geometry) ---

Geom Title=Existing Conditions

River Reach=LITTLE LLANO 018,Reach-1
Reach XY= 30
      2826663.75     10210927.00      2826663.75     10210924.00
      2826638.75     10210946.00      2826620.00     10210971.00
      2826570.00     10211052.00      2826557.50     10211084.00
      2826516.75     10211240.00      2826504.25     10211334.00
      2826488.75     10211396.00      2826488.75     10211427.00
      2826504.25     10211490.00      2826516.75     10211518.00
      2826554.25     10211568.00      2826623.00     10211631.00
      2826673.00     10211668.00      2826691.75     10211693.00
      2826757.50     10211762.00      2826776.25     10211787.00
      2826823.00     10211871.00      2826848.00     10211931.00
      2826862.00     10211977.00      2826874.00     10212006.00
      2826906.00     10212160.00      2826918.25     10212204.00
      2826895.00     10212289.00      2826898.50     10212370.00
      2826874.00     10212473.00      2826888.00     10212555.00
      2826903.25     10212612.00      2826905.00     10212651.00

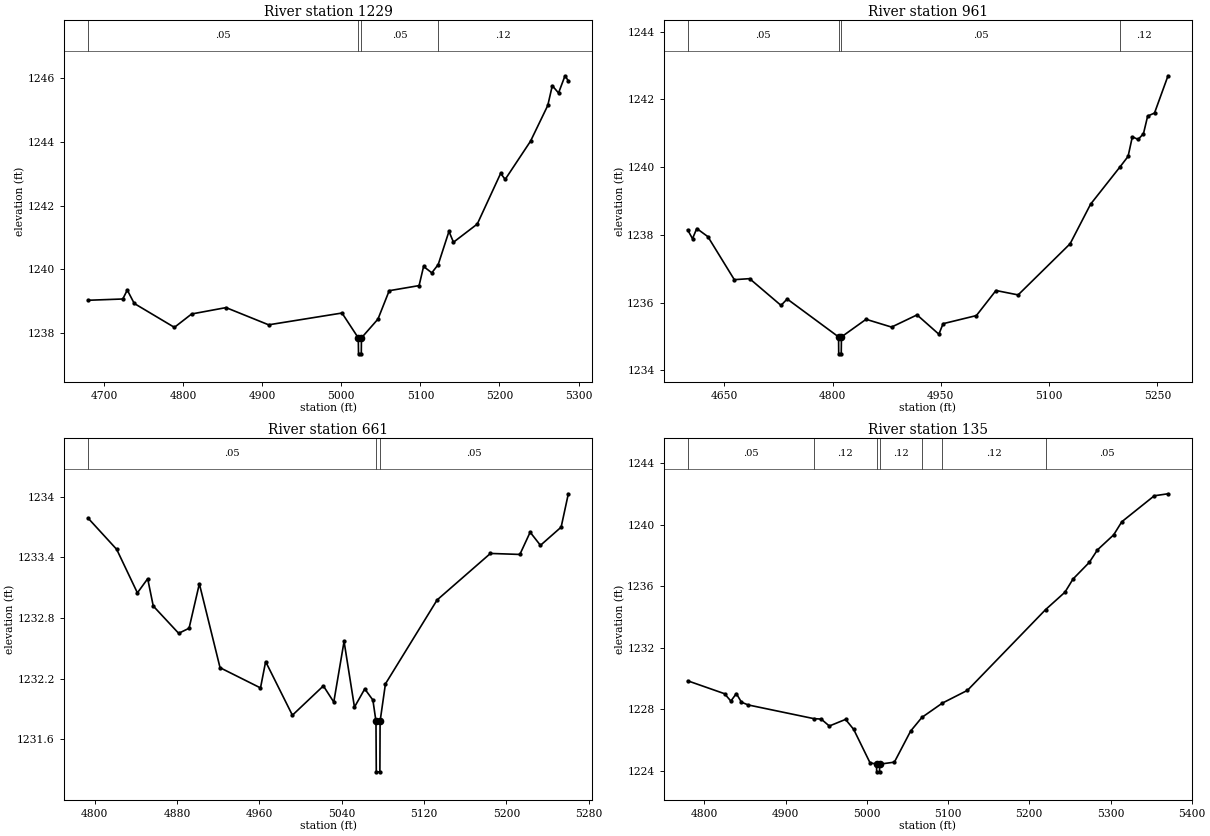
Type RM Length L Ch R = 1,1229,268,268,268
BEGIN DESCRIPTION:
Mapping XS c7c42a07
END DESCRIPTION:
XS GIS Cut Line= 2
      2826264.47     10211710.60      2826796.58     10211417.26
#Sta/Elev= 30
  4679.5 1239.03  4723.5 1239.07  4729.2 1239.35  4738.0 1238.93  4788.8 1238.18
  4810.6 1238.60  4854.1 1238.80  4908.0 1238.26  5000.8 1238.63  5021.4 1237.85
  5021.7 1237.35  5025.2 1237.35  5025.4 1237.85  5046.3 1238.44  5060.5 1239.33
  5098.3 1239.49  5104.0 1240.09  5114.4 1239.89  5122.5 1240.15  5136.1 1241.19
  5141.8 1240.85  5171.9 1241.42  5201.5 1243.01  5207.2 1242.82  5239.3 1244.02
  5261.1 1245.14  5266.8 1245.76  5274.7 1245.53  5282.9 1246.07  5287.1 1245.91
#Mann=4,-1,0
  4679.5    0.05       0  5021.4    0.05       0  5025.4    0.05       0
  5122.5    0.12       0
Bank Sta=5021.4,5025.4
Exp/Cntr=0.3,0.1

Type RM Length L Ch R = 1,961,300,300,300
BEGIN DESCRIPTION:
Mapping XS 28422def
END DESCRIPTION:
XS GIS Cut Line= 2
      2826395.85     10211952.22      2826960.83     10211600.91
#Sta/Elev= 30
  4599.3 1238.15  4606.0 1237.89  4611.9 1238.19  4627.3 1237.95  4663.9 1236.68
  4685.1 1236.71  4728.6 1235.92  4737.1 1236.11  4808.3 1234.99  4808.5 1234.49
  4812.0 1234.49  4812.3 1234.99  4846.4 1235.51  4881.7 1235.28  4917.0 1235.64
  4947.2 1235.07  4953.1 1235.38  4999.2 1235.62  5026.3 1236.36  5057.0 1236.23
  5129.0 1237.74  5157.4 1238.91  5198.5 1240.02  5209.3 1240.32  5215.2 1240.90
  5223.2 1240.82  5230.6 1240.99  5236.4 1241.51  5245.9 1241.60  5264.6 1242.70
#Mann=4,-1,0
  4599.3    0.05       0  4808.3    0.05       0  4812.3    0.05       0
  5198.5    0.12       0
Bank Sta=4808.3,4812.3
Exp/Cntr=0.3,0.1

Type RM Length L Ch R = 1,661,526,526,526
BEGIN DESCRIPTION:
Mapping XS 851c42c4
END DESCRIPTION:
XS GIS Cut Line= 2
      2826667.94     10212024.02      2827132.63     10211980.79
#Sta/Elev= 30
  4793.5 1233.79  4821.4 1233.48  4841.5 1233.05  4851.5 1233.19  4856.9 1232.92
  4881.6 1232.65  4891.7 1232.70  4901.7 1233.14  4921.8 1232.31  4961.1 1232.11
  4966.1 1232.37  4992.1 1231.84  5022.2 1232.13  5032.3 1231.97  5042.3 1232.57
  5052.4 1231.92  5062.4 1232.10  5070.3 1231.99  5073.3 1231.78  5073.6 1231.28
  5077.1 1231.28  5077.3 1231.78  5082.5 1232.15  5132.7 1232.98  5184.5 1233.44
  5213.1 1233.43  5223.1 1233.65  5233.1 1233.52  5253.2 1233.70  5260.2 1234.03
#Mann=3,-1,0
  4793.5    0.05       0  5073.3    0.05       0  5077.3    0.05       0
Bank Sta=5073.3,5077.3
Exp/Cntr=0.3,0.1

Type RM Length L Ch R = 1,135,0,0,0
BEGIN DESCRIPTION:
LITTLE LLANO 018 2.0
END DESCRIPTION:
XS GIS Cut Line= 3
      2826724.12     10212390.79      2826820.47     10212517.55
      2827252.55     10212526.89
#Sta/Elev= 30
  4779.4 1229.86  4824.8 1229.02  4832.6 1228.54  4839.3 1229.03  4845.6 1228.47
  4853.9 1228.29  4934.7 1227.40  4943.8 1227.37  4953.8 1226.92  4973.8 1227.35
  4983.8 1226.70  5003.9 1224.53  5011.9 1224.44  5012.1 1223.94  5015.6 1223.94
  5015.9 1224.44  5033.9 1224.57  5053.9 1226.59  5067.8 1227.48  5093.0 1228.41
  5123.9 1229.24  5220.1 1234.49  5243.9 1235.62  5253.9 1236.48  5273.9 1237.56
  5283.9 1238.37  5303.9 1239.35  5313.9 1240.20  5353.9 1241.89  5370.8 1242.02
#Mann=7,-1,0
  4779.4    0.05       0  4934.7    0.12       0  5011.9    0.07       0
  5015.9    0.12       0  5067.8    0.05       0  5093.0    0.12       0
  5220.1    0.05       0
Bank Sta=5011.9,5015.9
Exp/Cntr=0.3,0.1

Chan Stop Cuts=-1