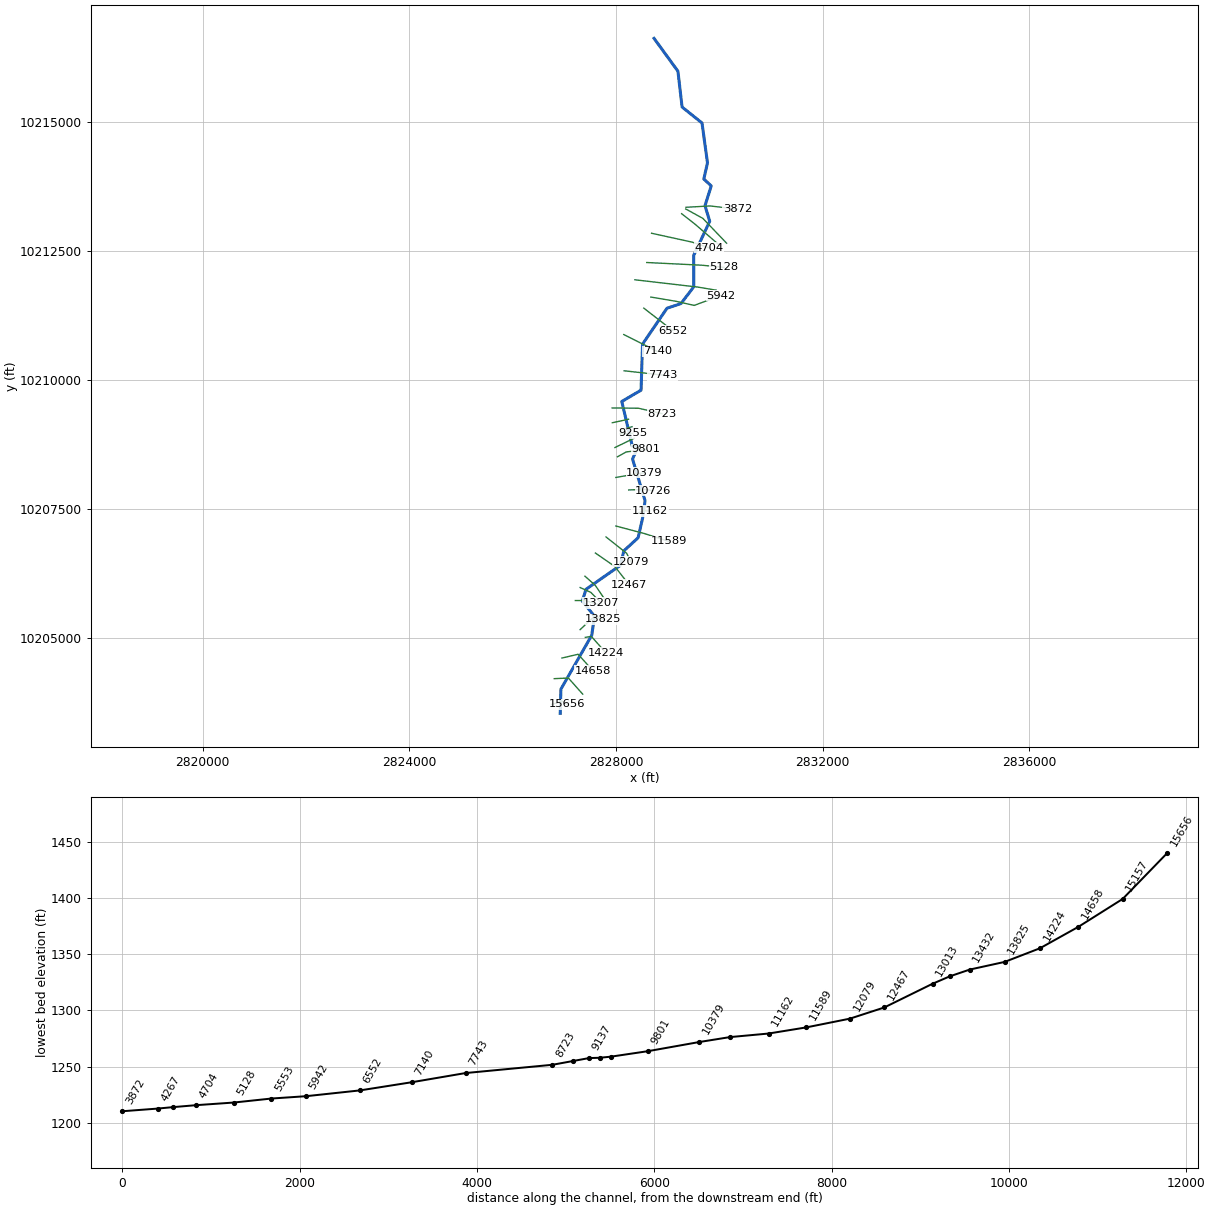
--- LITTLE LLANO 019.prj (project) ---

Proj Title=LITTLE LLANO 019 Base Level Engineering
Current Plan=p01
Default Exp/Contr=0.3,0.1
English Units
Geom File=g01
Flow File=f01
Plan File=p01
BEGIN DESCRIPTION:
LITTLE LLANO 019
END DESCRIPTION:

--- LITTLE LLANO 019.p01 (plan) ---

Plan Title=Multiple Run
Short Identifier=Multiple
Geom File=g01
Flow File=f01
Subcritical Flow
K Sum by GR= 0
Std Step Tol= 0.01
Critical Tol= 0.01
Num of Std Step Trials= 20
Max Error Tol= 0.3
Flow Tol Ratio= 0.001
Split Flow NTrial= 30
Split Flow Tol= 0.02
Split Flow Ratio= 0.02
Log Output Level= 0
Friction Slope Method= 1
Unsteady Friction Slope Method= 2
Unsteady Bridges Friction Slope Method= 1
Parabolic Critical Depth
Global Vel Dist=  1 , 1 , 1
Global Log Level= 0
CheckData=True
Encroach Param= -1, 0, 0, 0
BEGIN DESCRIPTION:
Multiple Run
END DESCRIPTION:

--- LITTLE LLANO 019.f01 (steady flow) ---

Flow Title=Multiple
Number of Profiles=7
Profile Names=10-year,25-year,50-year,1pct_min,100-year,1pct_plu,500-year
River Rch & RM= LITTLE LLANO 019,Reach-1,15656
     144     218     483     423     667    1054    1006
River Rch & RM= LITTLE LLANO 019,Reach-1,11589
     412     667    1414    1114    2000    3589    2943
River Rch & RM= LITTLE LLANO 019,Reach-1,5553
     670    1122    2283    1704    3259    6233    4748
Boundary for River Rch & Prof#=LITTLE LLANO 019,Reach-1,1
Up Type=0
Dn Type=3
Dn Slope=0.005
Boundary for River Rch & Prof#=LITTLE LLANO 019,Reach-1,2
Up Type=0
Dn Type=3
Dn Slope=0.005
Boundary for River Rch & Prof#=LITTLE LLANO 019,Reach-1,3
Up Type=0
Dn Type=3
Dn Slope=0.005
Boundary for River Rch & Prof#=LITTLE LLANO 019,Reach-1,4
Up Type=0
Dn Type=3
Dn Slope=0.005
Boundary for River Rch & Prof#=LITTLE LLANO 019,Reach-1,5
Up Type=0
Dn Type=3
Dn Slope=0.005
Boundary for River Rch & Prof#=LITTLE LLANO 019,Reach-1,6
Up Type=0
Dn Type=3
Dn Slope=0.005
Boundary for River Rch & Prof#=LITTLE LLANO 019,Reach-1,7
Up Type=0
Dn Type=3
Dn Slope=0.005

--- LITTLE LLANO 019.g01 (geometry) ---

Geom Title=Existing Conditions

River Reach=LITTLE LLANO 019,Reach-1
Reach XY= 30
      2826921.00     10203530.00      2826934.00     10204000.00
      2827531.00     10205044.00      2827583.50     10205413.00
      2827349.00     10205705.00      2827417.75     10205934.00
      2828080.50     10206397.00      2828153.50     10206682.00
      2828427.75     10206934.00      2828515.00     10207316.00
      2828562.75     10207651.00      2828320.50     10208461.00
      2828434.75     10208714.00      2828315.75     10208711.00
      2828112.25     10209576.00      2828485.50     10209796.00
      2828513.50     10210687.00      2828987.25     10211384.00
      2829258.00     10211474.00      2829505.50     10211800.00
      2829504.00     10212408.00      2829813.75     10213069.00
      2829722.75     10213372.00      2829843.25     10213755.00
      2829699.75     10213889.00      2829771.00     10214202.00
      2829664.75     10214975.00      2829279.25     10215284.00
      2829198.75     10215979.00      2828736.25     10216616.00

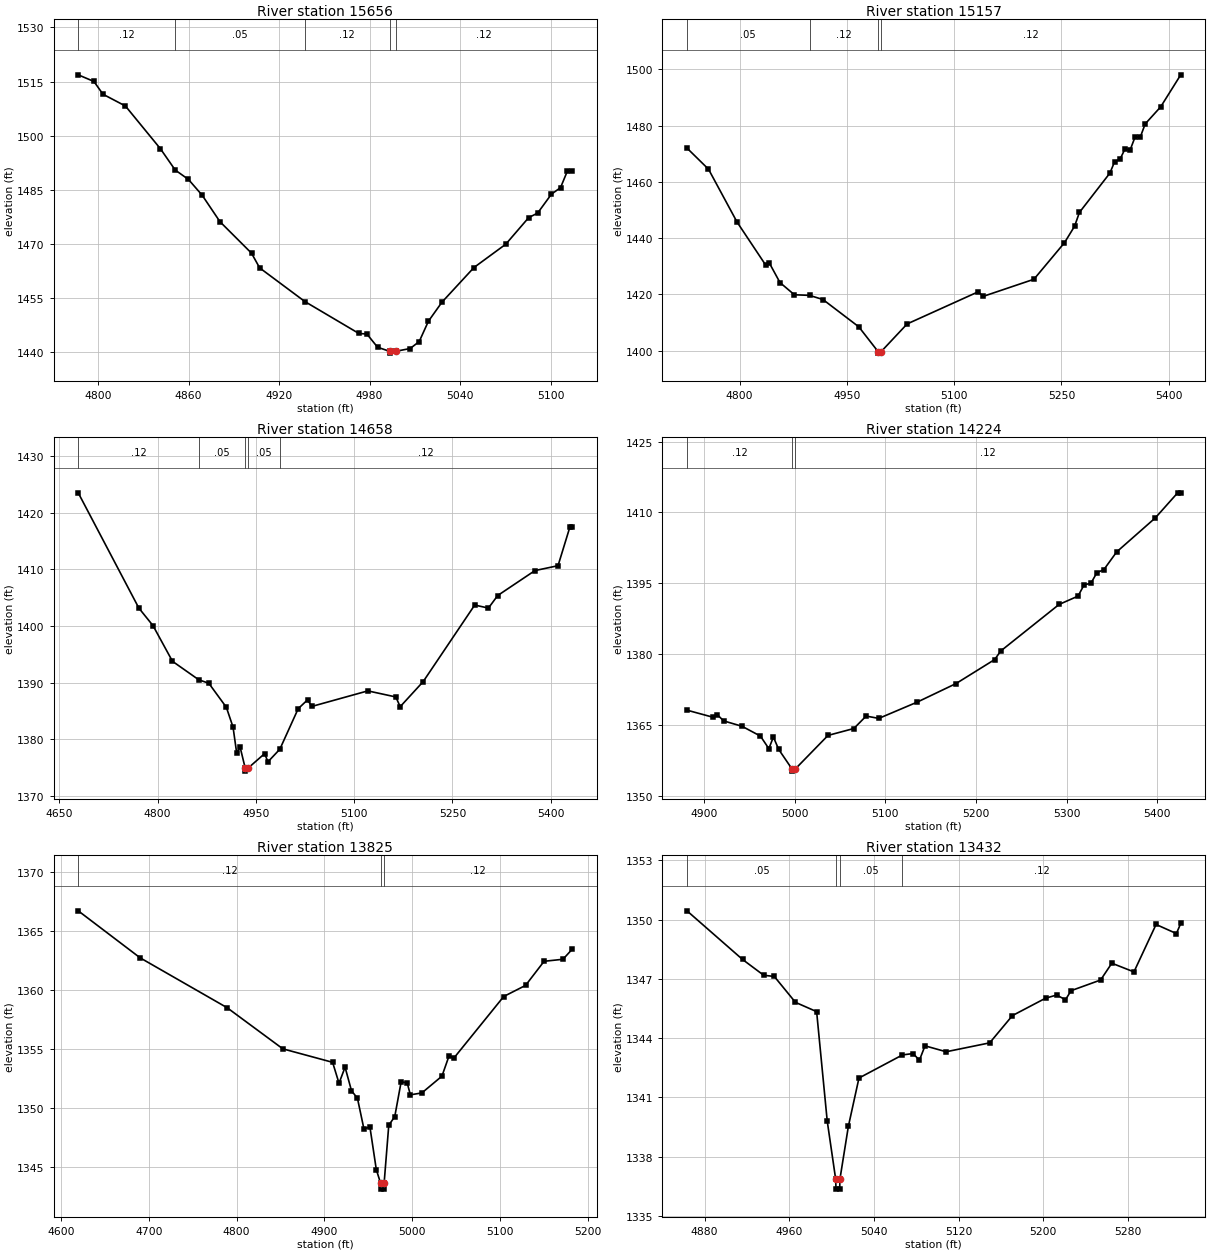
Type RM Length L Ch R = 1,15656,499,499,499
BEGIN DESCRIPTION:
LITTLE LLANO 019 27.0
END DESCRIPTION:
XS GIS Cut Line= 3
      2826755.73     10203703.12      2826959.75     10203765.00
      2827055.71     10203703.09
#Sta/Elev= 30
  4786.8 1516.87  4797.2 1515.03  4803.2 1511.49  4818.1 1508.22  4841.3 1496.37
  4851.1 1490.47  4859.9 1487.85  4869.0 1483.47  4880.8 1476.13  4901.7 1467.41
  4907.1 1463.33  4937.1 1453.99  4972.9 1445.14  4978.2 1444.99  4985.3 1441.32
  4993.3 1440.19  4993.5 1439.69  4997.3 1440.19  5006.9 1440.97  5012.9 1442.90
  5019.0 1448.54  5028.0 1453.83  5049.2 1463.43  5070.3 1469.90  5085.5 1477.28
  5091.4 1478.52  5100.6 1483.79  5106.6 1485.58  5111.2 1490.24  5114.2 1490.24
#Mann=5,-1,0
  4786.8    0.12       0  4851.1    0.05       0  4937.1    0.12       0
  4993.3    0.07       0  4997.3    0.12       0
Bank Sta=4993.3,4997.3
Exp/Cntr=0.3,0.1

Type RM Length L Ch R = 1,15157,499,499,499
BEGIN DESCRIPTION:
LITTLE LLANO 019 26.0
END DESCRIPTION:
XS GIS Cut Line= 3
      2826805.66     10204203.11      2827079.00     10204215.00
      2827355.67     10203903.13
#Sta/Elev= 30
  4726.4 1471.99  4756.5 1464.49  4796.5 1445.69  4836.5 1430.43  4841.5 1431.21
  4856.5 1424.22  4876.6 1419.90  4897.8 1419.68  4916.6 1418.20  4966.7 1408.51
  4993.8 1399.67  4994.1 1399.17  4997.8 1399.67  5034.3 1409.54  5133.8 1420.96
  5140.5 1419.31  5211.6 1425.40  5254.3 1438.37  5268.5 1444.25  5275.2 1449.13
  5317.8 1463.09  5324.5 1467.17  5332.0 1468.04  5338.7 1471.53  5346.3 1471.42
  5352.9 1475.83  5360.5 1475.99  5367.2 1480.57  5388.9 1486.64  5416.9 1498.00
#Mann=4,-1,0
  4726.4    0.05       0  4897.8    0.12       0  4993.8    0.07       0
  4997.8    0.12       0
Bank Sta=4993.8,4997.8
Exp/Cntr=0.3,0.1

Type RM Length L Ch R = 1,14658,434,434,434
BEGIN DESCRIPTION:
LITTLE LLANO 019 25.0
END DESCRIPTION:
XS GIS Cut Line= 3
      2826955.64     10204603.10      2827268.25     10204676.00
      2827555.69     10204353.10
#Sta/Elev= 30
  4679.0 1423.51  4771.5 1403.17  4793.1 1400.07  4822.8 1393.78  4863.0 1390.51
  4878.2 1389.91  4905.0 1385.66  4915.2 1382.16  4920.8 1377.55  4925.9 1378.68
  4933.8 1374.90  4934.0 1374.40  4937.8 1374.90  4963.3 1377.48  4968.5 1376.05
  4986.6 1378.27  5014.6 1385.42  5028.8 1386.97  5035.5 1385.82  5120.8 1388.56
  5163.5 1387.49  5170.2 1385.77  5205.3 1390.20  5283.9 1403.71  5304.8 1403.17
  5319.0 1405.39  5375.8 1409.79  5411.0 1410.65  5428.9 1417.40  5432.3 1417.40
#Mann=5,-1,0
  4679.0    0.12       0  4863.0    0.05       0  4933.8    0.07       0
  4937.8    0.05       0  4986.6    0.12       0
Bank Sta=4933.8,4937.8
Exp/Cntr=0.3,0.1

Type RM Length L Ch R = 1,14224,399,399,399
BEGIN DESCRIPTION:
LITTLE LLANO 019 24.0
END DESCRIPTION:
XS GIS Cut Line= 3
      2827405.66     10205003.11      2827523.25     10205022.00
      2827805.70     10204703.10
#Sta/Elev= 30
  4880.9 1368.20  4909.3 1366.72  4914.4 1367.24  4921.4 1365.93  4941.7 1364.79
  4962.0 1362.72  4971.3 1360.06  4976.3 1362.52  4982.2 1359.89  4996.7 1355.81
  4997.0 1355.31  5000.7 1355.81  5036.6 1362.86  5065.1 1364.32  5078.7 1366.95
  5092.7 1366.46  5135.3 1369.92  5178.0 1373.83  5220.6 1378.90  5227.3 1380.71
  5291.7 1390.55  5312.6 1392.31  5319.3 1394.68  5326.9 1395.05  5333.5 1397.28
  5341.1 1397.90  5355.3 1401.66  5398.0 1408.86  5422.6 1414.15  5426.0 1414.15
#Mann=3,-1,0
  4880.9    0.12       0  4996.7    0.07       0  5000.7    0.12       0
Bank Sta=4996.7,5000.7
Exp/Cntr=0.3,0.1

Type RM Length L Ch R = 1,13825,393,393,393
BEGIN DESCRIPTION:
LITTLE LLANO 019 23.0
END DESCRIPTION:
XS GIS Cut Line= 3
      2827305.70     10205153.13      2827583.50     10205413.00
      2827755.68     10205353.11
#Sta/Elev= 30
  4619.6 1366.71  4690.2 1362.73  4789.3 1358.51  4852.8 1355.03  4909.5 1353.89
  4916.8 1352.12  4923.7 1353.48  4931.0 1351.49  4937.8 1350.85  4945.2 1348.25
  4952.0 1348.43  4959.3 1344.81  4964.2 1343.66  4964.4 1343.16  4967.9 1343.16
  4968.2 1343.66  4973.5 1348.57  4980.3 1349.29  4987.6 1352.24  4994.5 1352.15
  4998.1 1351.14  5011.2 1351.30  5034.1 1352.72  5042.3 1354.46  5047.6 1354.24
  5104.5 1359.46  5129.4 1360.40  5150.5 1362.44  5172.0 1362.61  5182.3 1363.44
#Mann=3,-1,0
  4619.6    0.12       0  4964.2    0.07       0  4968.2    0.12       0
Bank Sta=4964.2,4968.2
Exp/Cntr=0.3,0.1

Type RM Length L Ch R = 1,13432,225,225,225
BEGIN DESCRIPTION:
LITTLE LLANO 019 22.0
END DESCRIPTION:
XS GIS Cut Line= 3
      2827213.16     10205717.78      2827399.64     10205717.78
      2827668.05     10205637.99
#Sta/Elev= 30
  4863.3 1350.44  4915.8 1347.98  4935.8 1347.18  4945.8 1347.12  4965.8 1345.81
  4985.8 1345.34  4995.8 1339.81  5003.8 1336.86  5004.1 1336.36  5007.6 1336.36
  5007.8 1336.86  5015.8 1339.54  5025.8 1341.98  5066.9 1343.15  5077.0 1343.22
  5082.9 1342.88  5088.2 1343.61  5108.2 1343.31  5149.3 1343.76  5170.8 1345.14
  5202.1 1346.02  5212.6 1346.18  5220.9 1345.94  5226.2 1346.40  5254.1 1346.94
  5264.7 1347.79  5285.6 1347.35  5306.5 1349.75  5325.7 1349.29  5329.8 1349.80
#Mann=4,-1,0
  4863.3    0.05       0  5003.8    0.05       0  5007.8    0.05       0
  5066.9    0.12       0
Bank Sta=5003.8,5007.8
Exp/Cntr=0.3,0.1

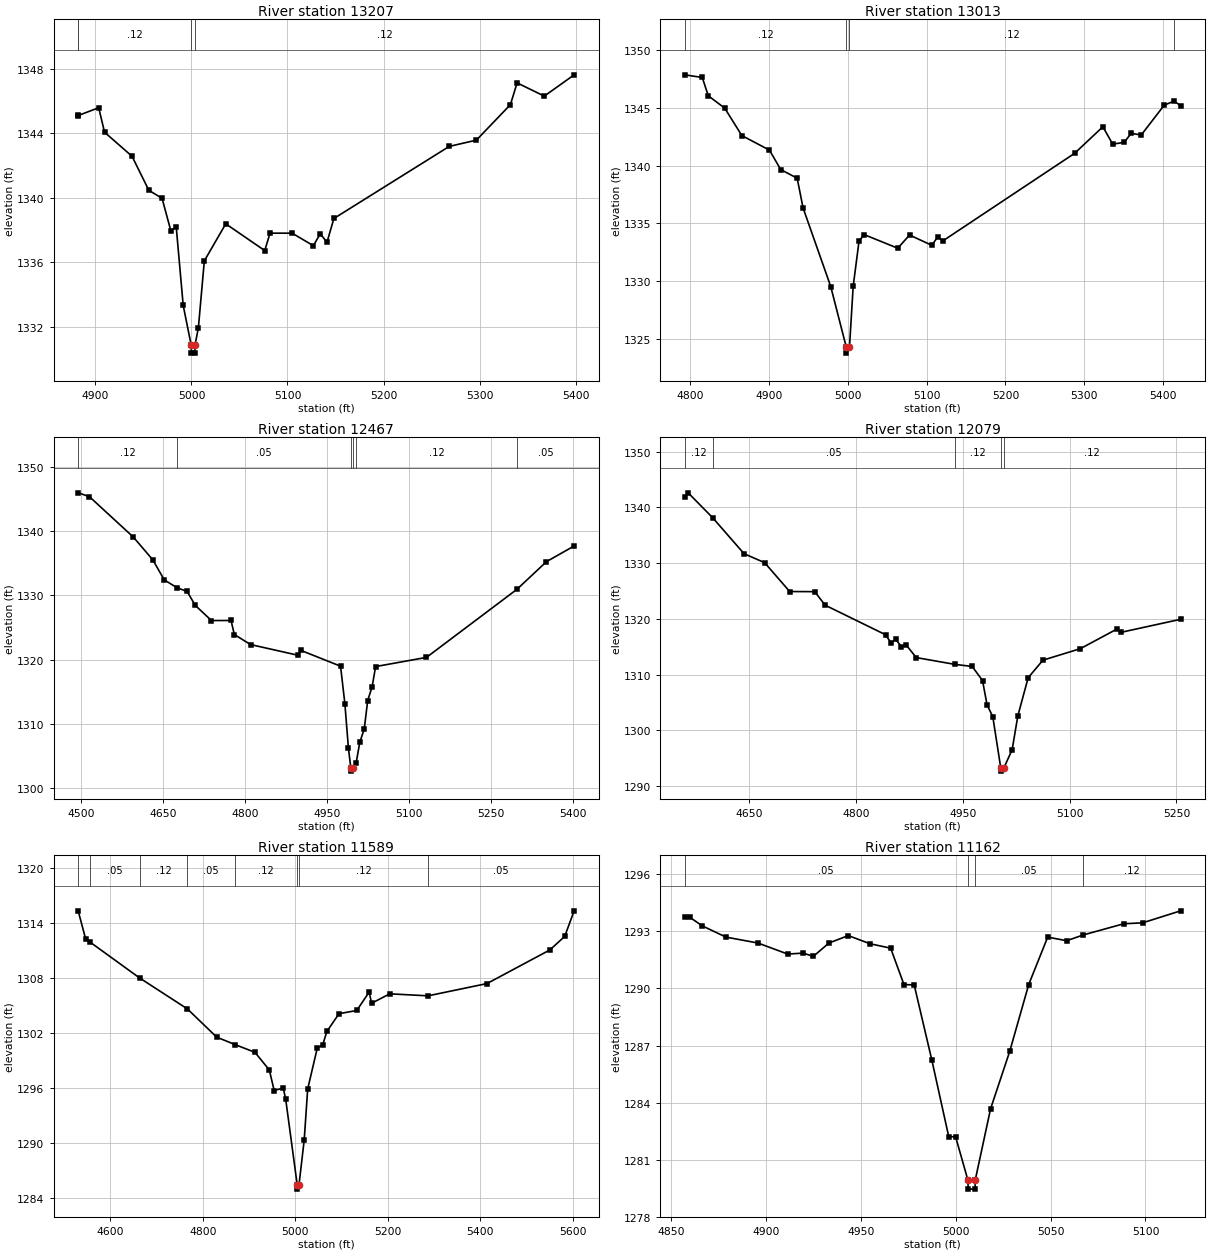
Type RM Length L Ch R = 1,13207,194,194,194
BEGIN DESCRIPTION:
Mapping XS 5cbe1425
END DESCRIPTION:
XS GIS Cut Line= 3
      2827306.36     10205969.70      2827513.49     10205875.22
      2827715.76     10205669.31
#Sta/Elev= 30
  4882.2 1345.08  4882.3 1345.09  4903.4 1345.57  4909.5 1344.05  4938.1 1342.56
  4955.6 1340.45  4969.4 1339.95  4978.6 1337.92  4984.1 1338.20  4991.4 1333.31
  4999.7 1330.85  4999.9 1330.35  5003.4 1330.35  5003.7 1330.85  5007.2 1331.92
  5013.4 1336.07  5035.7 1338.37  5076.3 1336.71  5081.8 1337.79  5104.8 1337.79
  5127.0 1337.01  5134.1 1337.76  5141.1 1337.22  5148.3 1338.70  5268.4 1343.17
  5296.7 1343.56  5332.1 1345.76  5339.1 1347.11  5367.4 1346.29  5398.5 1347.61
#Mann=4,-1,0
  4882.2    0.05       0  4882.3    0.12       0  4999.7    0.07       0
  5003.7    0.12       0
Bank Sta=4999.7,5003.7
Exp/Cntr=0.3,0.1

Type RM Length L Ch R = 1,13013,546,546,546
BEGIN DESCRIPTION:
LITTLE LLANO 019 21.0
END DESCRIPTION:
XS GIS Cut Line= 3
      2827399.63     10206188.91      2827598.26     10206013.29
      2827802.94     10205711.73
#Sta/Elev= 30
  4792.9 1347.84  4815.1 1347.61  4822.7 1346.03  4843.6 1344.96  4865.3 1342.59
  4900.4 1341.33  4914.7 1339.65  4935.6 1338.90  4943.1 1336.33  4978.2 1329.54
  4998.0 1324.28  4998.2 1323.78  5002.0 1324.28  5006.7 1329.55  5014.2 1333.50
  5020.9 1334.02  5063.3 1332.85  5078.3 1333.99  5106.6 1333.10  5114.2 1333.85
  5120.3 1333.47  5287.8 1341.05  5323.8 1343.35  5336.2 1341.85  5350.8 1342.00
  5359.7 1342.78  5372.5 1342.64  5401.7 1345.22  5414.3 1345.57  5422.5 1345.17
#Mann=4,-1,0
  4792.9    0.12       0  4998.0    0.07       0  5002.0    0.12       0
  5414.3    0.05       0
Bank Sta=4998,5002
Exp/Cntr=0.3,0.1

Type RM Length L Ch R = 1,12467,388,388,388
BEGIN DESCRIPTION:
LITTLE LLANO 019 20.0
END DESCRIPTION:
XS GIS Cut Line= 3
      2827601.88     10206638.22      2827977.33     10206377.82
      2828254.65     10206021.79
#Sta/Elev= 30
  4494.5 1345.99  4514.8 1345.39  4595.2 1339.10  4631.0 1335.54  4651.9 1332.42
  4675.3 1331.21  4693.8 1330.62  4708.7 1328.45  4738.4 1326.09  4774.2 1326.10
  4780.3 1323.91  4810.0 1322.35  4896.5 1320.69  4902.5 1321.43  4974.8 1318.98
  4982.7 1313.16  4989.2 1306.22  4993.6 1303.13  4993.8 1302.63  4997.6 1303.13
  5003.2 1303.83  5010.1 1307.15  5018.2 1309.18  5024.5 1313.62  5032.7 1315.80
  5039.0 1318.92  5132.2 1320.35  5298.1 1330.97  5352.0 1335.27  5402.7 1337.71
#Mann=6,-1,0
  4494.5    0.12       0  4675.3    0.05       0  4993.6    0.05       0
  4997.6    0.05       0  5003.2    0.12       0  5298.1    0.05       0
Bank Sta=4993.6,4997.6
Exp/Cntr=0.3,0.1

Type RM Length L Ch R = 1,12079,490,490,490
BEGIN DESCRIPTION:
LITTLE LLANO 019 19.0
END DESCRIPTION:
XS GIS Cut Line= 3
      2827806.55     10206950.68      2828206.23     10206633.36
      2828290.36     10206467.50
#Sta/Elev= 30
  4559.6 1341.92  4564.3 1342.62  4598.7 1338.16  4642.8 1331.70  4671.7 1330.09
  4706.9 1324.91  4742.1 1324.89  4756.6 1322.47  4841.5 1317.16  4849.5 1315.65
  4855.9 1316.33  4863.9 1314.98  4870.3 1315.35  4884.7 1313.06  4939.0 1311.84
  4963.2 1311.47  4977.7 1308.94  4984.1 1304.56  4992.1 1302.48  5003.4 1293.19
  5003.6 1292.69  5007.4 1293.19  5019.3 1296.53  5027.3 1302.61  5041.8 1309.45
  5062.6 1312.60  5115.1 1314.66  5166.9 1318.21  5172.5 1317.60  5255.9 1319.93
#Mann=5,-1,0
  4559.6    0.12       0  4598.7    0.05       0  4939.0    0.12       0
  5003.4    0.07       0  5007.4    0.12       0
Bank Sta=5003.4,5007.4
Exp/Cntr=0.3,0.1

Type RM Length L Ch R = 1,11589,427,427,427
BEGIN DESCRIPTION:
LITTLE LLANO 019 18.0
END DESCRIPTION:
XS GIS Cut Line= 3
      2827996.74     10207162.60      2828553.81     10207014.85
      2829024.96     10206863.46
#Sta/Elev= 30
  4531.3 1315.25  4547.3 1312.21  4556.5 1311.91  4663.7 1307.99  4767.0 1304.61
  4830.2 1301.53  4869.9 1300.72  4913.0 1299.87  4944.0 1297.94  4954.4 1295.70
  4973.9 1295.98  4979.1 1294.83  5004.1 1285.44  5004.4 1284.94  5008.1 1285.44
  5019.3 1290.31  5026.8 1295.87  5047.5 1300.33  5059.5 1300.71  5068.2 1302.15
  5094.5 1304.09  5132.8 1304.44  5159.6 1306.45  5164.9 1305.23  5204.1 1306.26
  5286.8 1306.04  5414.2 1307.38  5550.0 1311.05  5582.1 1312.53  5602.5 1315.32
#Mann=8,-1,0
  4531.3    0.12       0  4556.5    0.05       0  4663.7    0.12       0
  4767.0    0.05       0  4869.9    0.12       0  5004.1    0.07       0
  5008.1    0.12       0  5286.8    0.05       0
Bank Sta=5004.1,5008.1
Exp/Cntr=0.3,0.1

Type RM Length L Ch R = 1,11162,436,436,436
BEGIN DESCRIPTION:
LITTLE LLANO 019 17.0
END DESCRIPTION:
XS GIS Cut Line= 3
      2828405.64     10207403.09      2828537.25     10207458.00
      2828655.65     10207453.11
#Sta/Elev= 30
  4857.4 1293.72  4860.2 1293.72  4866.6 1293.28  4879.1 1292.69  4895.9 1292.38
  4911.6 1291.80  4919.7 1291.85  4925.1 1291.68  4933.3 1292.38  4943.5 1292.77
  4955.0 1292.34  4965.8 1292.11  4972.8 1290.20  4978.2 1290.18  4987.5 1286.23
  4996.4 1282.21  5000.0 1282.21  5006.4 1279.96  5006.7 1279.46  5010.2 1279.46
  5010.4 1279.96  5018.4 1283.67  5028.5 1286.69  5038.5 1290.20  5048.5 1292.69
  5058.5 1292.50  5067.1 1292.80  5088.5 1293.39  5098.5 1293.44  5118.5 1294.07
#Mann=4,-1,0
  4857.4    0.05       0  5006.4    0.03       0  5010.4    0.05       0
  5067.1    0.12       0
Bank Sta=5006.4,5010.4
Exp/Cntr=0.3,0.1

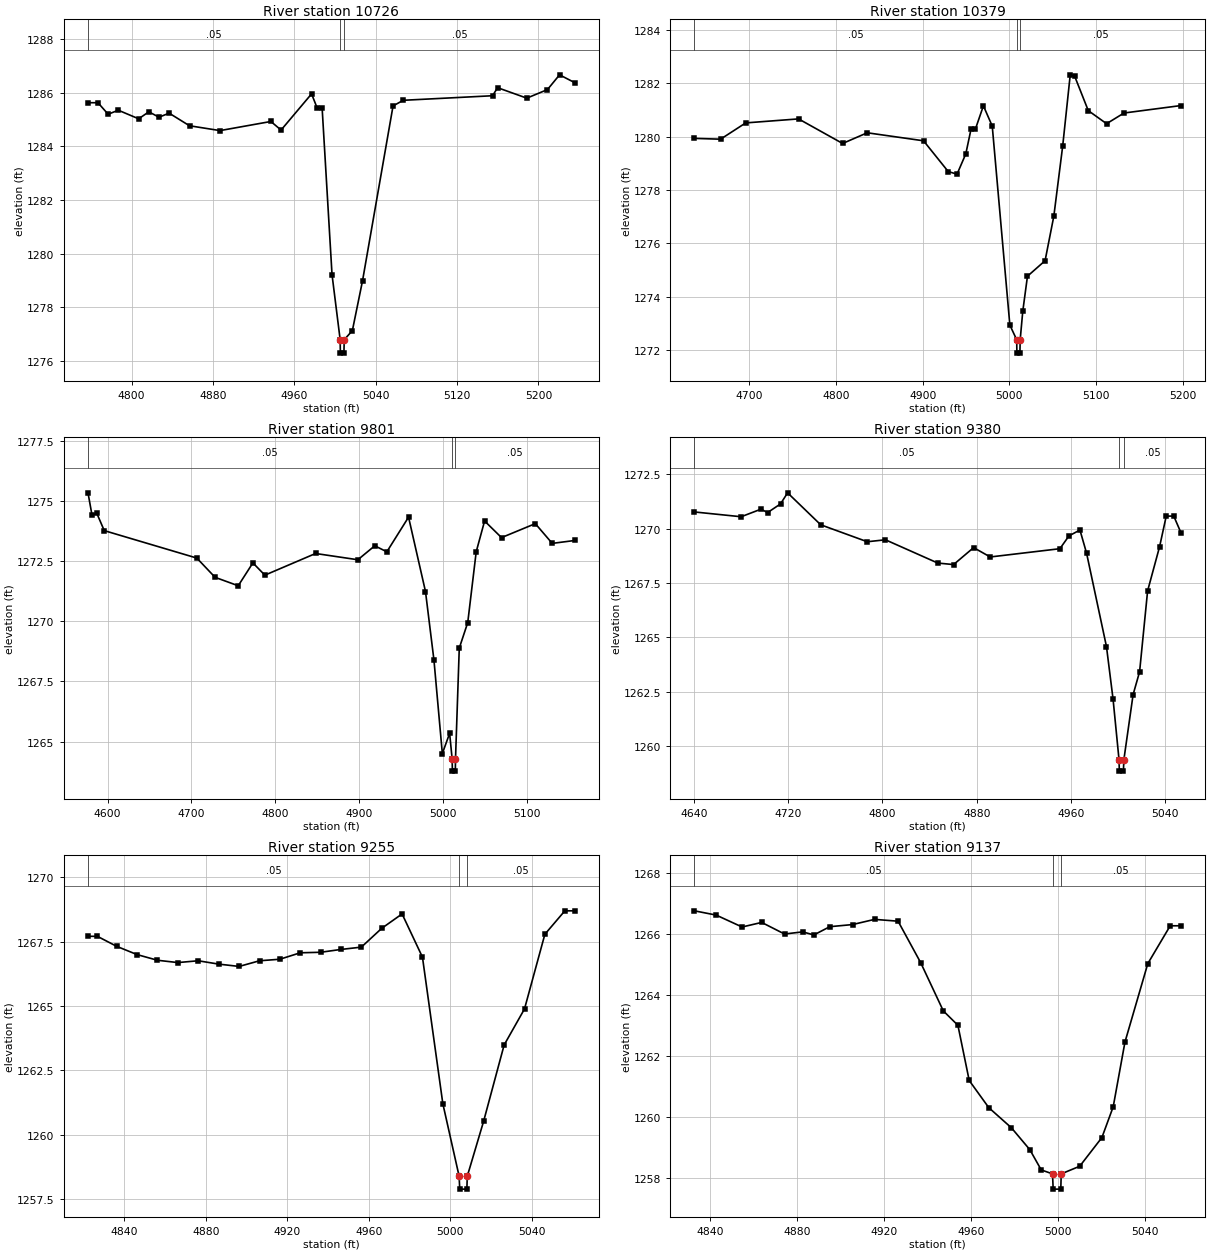
Type RM Length L Ch R = 1,10726,347,347,347
BEGIN DESCRIPTION:
LITTLE LLANO 019 16.0
END DESCRIPTION:
XS GIS Cut Line= 3
      2828245.94     10207861.41      2828567.08     10207870.96
      2828722.06     10207845.13
#Sta/Elev= 30
  4757.2 1285.63  4767.0 1285.63  4777.0 1285.20  4787.0 1285.35  4807.0 1285.03
  4817.0 1285.29  4827.0 1285.09  4837.0 1285.24  4857.0 1284.77  4887.0 1284.59
  4937.0 1284.93  4947.0 1284.61  4977.0 1285.96  4982.4 1285.44  4987.4 1285.42
  4997.1 1279.22  5005.1 1276.79  5005.3 1276.29  5008.8 1276.29  5009.1 1276.79
  5017.1 1277.13  5027.1 1278.99  5057.1 1285.51  5067.1 1285.72  5154.9 1285.89
  5159.9 1286.19  5188.6 1285.80  5208.9 1286.12  5220.8 1286.67  5235.6 1286.38
#Mann=3,-1,0
  4757.2    0.05       0  5005.1    0.03       0  5009.1    0.05       0
Bank Sta=5005.1,5009.1
Exp/Cntr=0.3,0.1

Type RM Length L Ch R = 1,10379,578,578,578
BEGIN DESCRIPTION:
LITTLE LLANO 019 15.0
END DESCRIPTION:
XS GIS Cut Line= 3
      2827997.43     10208103.60      2828448.80     10208181.72
      2828551.00     10208193.85
#Sta/Elev= 30
  4636.9 1279.93  4667.0 1279.90  4696.0 1280.51  4756.9 1280.66  4807.7 1279.74
  4836.1 1280.14  4901.0 1279.84  4929.4 1278.69  4939.6 1278.59  4949.7 1279.35
  4955.7 1280.27  4960.7 1280.27  4970.0 1281.15  4980.2 1280.39  5000.5 1272.94
  5008.4 1272.39  5008.6 1271.89  5012.1 1271.89  5012.4 1272.39  5015.4 1273.46
  5020.8 1274.77  5041.1 1275.35  5051.2 1277.02  5061.4 1279.64  5070.1 1282.31
  5075.2 1282.26  5090.9 1280.97  5112.0 1280.48  5132.1 1280.88  5197.9 1281.16
#Mann=3,-1,0
  4636.9    0.05       0  5008.4    0.05       0  5012.4    0.05       0
Bank Sta=5008.4,5012.4
Exp/Cntr=0.3,0.1

Type RM Length L Ch R = 1,9801,421,421,421
BEGIN DESCRIPTION:
LITTLE LLANO 019 14.0
END DESCRIPTION:
XS GIS Cut Line= 3
      2828028.64     10208504.63      2828197.60     10208597.51
      2828582.19     10208646.50
#Sta/Elev= 30
  4576.6 1275.33  4581.4 1274.40  4587.1 1274.48  4596.0 1273.76  4706.4 1272.62
  4728.2 1271.82  4755.8 1271.47  4773.3 1272.42  4787.6 1271.91  4848.1 1272.81
  4898.5 1272.55  4918.7 1273.13  4933.1 1272.88  4959.0 1274.32  4979.2 1271.23
  4989.3 1268.38  4999.3 1264.50  5008.0 1265.34  5011.0 1264.27  5011.3 1263.77
  5014.8 1263.77  5015.0 1264.27  5019.5 1268.88  5029.6 1269.94  5039.7 1272.88
  5049.7 1274.16  5069.9 1273.47  5110.2 1274.05  5130.4 1273.23  5157.1 1273.35
#Mann=3,-1,0
  4576.6    0.05       0  5011.0    0.05       0  5015.0    0.05       0
Bank Sta=5011,5015
Exp/Cntr=0.3,0.1

Type RM Length L Ch R = 1,9380,125,125,125
BEGIN DESCRIPTION:
LITTLE LLANO 019 13.0
END DESCRIPTION:
XS GIS Cut Line= 2
      2827980.07     10208683.31      2828351.21     10208864.03
#Sta/Elev= 30
  4640.5 1270.77  4680.1 1270.55  4697.0 1270.90  4702.5 1270.74  4713.5 1271.14
  4719.5 1271.65  4747.6 1270.18  4787.1 1269.40  4802.5 1269.49  4846.9 1268.42
  4860.3 1268.35  4877.3 1269.13  4891.4 1268.70  4950.5 1269.08  4958.2 1269.67
  4967.5 1269.94  4973.1 1268.88  4990.0 1264.58  4995.6 1262.16  5000.7 1259.35
  5000.9 1258.85  5004.4 1258.85  5004.7 1259.35  5012.6 1262.37  5018.1 1263.42
  5024.9 1267.14  5035.1 1269.18  5040.7 1270.58  5047.1 1270.58  5053.3 1269.80
#Mann=3,-1,0
  4640.5    0.05       0  5000.7    0.03       0  5004.7    0.05       0
Bank Sta=5000.7,5004.7
Exp/Cntr=0.3,0.1

Type RM Length L Ch R = 1,9255,118,118,118
BEGIN DESCRIPTION:
Mapping XS e5428ef4
END DESCRIPTION:
XS GIS Cut Line= 2
      2828081.57     10208948.79      2828320.30     10208957.83
#Sta/Elev= 29
  4822.2 1267.71  4826.8 1267.71  4836.3 1267.32  4846.3 1267.00  4856.3 1266.78
  4866.3 1266.69  4876.3 1266.76  4886.4 1266.63  4896.4 1266.54  4906.4 1266.76
  4916.4 1266.82  4926.4 1267.07  4936.4 1267.09  4946.4 1267.20  4956.4 1267.29
  4966.4 1268.02  4976.4 1268.58  4986.4 1266.90  4996.4 1261.21  5004.4 1258.39
  5004.7 1257.89  5008.2 1257.89  5008.4 1258.39  5016.4 1260.52  5026.5 1263.49
  5036.5 1264.89  5046.5 1267.79  5056.3 1268.70  5061.1 1268.70
#Mann=3,-1,0
  4822.2    0.05       0  5004.4    0.05       0  5008.4    0.05       0
Bank Sta=5004.4,5008.4
Exp/Cntr=0.3,0.1

Type RM Length L Ch R = 1,9137,178,178,178
BEGIN DESCRIPTION:
Mapping XS 2b8a7ef2
END DESCRIPTION:
XS GIS Cut Line= 2
      2828096.07     10209022.94      2828310.36     10209087.13
#Sta/Elev= 30
  4832.9 1266.76  4842.9 1266.62  4854.8 1266.23  4863.8 1266.38  4874.3 1266.00
  4882.6 1266.07  4887.8 1265.97  4895.1 1266.24  4905.6 1266.31  4915.7 1266.48
  4926.5 1266.42  4936.9 1265.06  4947.3 1263.48  4954.0 1263.01  4959.2 1261.20
  4968.2 1260.31  4978.6 1259.65  4987.1 1258.93  4992.3 1258.27  4997.5 1258.14
  4997.8 1257.64  5001.3 1257.64  5001.5 1258.14  5010.0 1258.39  5020.2 1259.33
  5025.4 1260.34  5030.8 1262.46  5041.3 1265.03  5051.6 1266.27  5056.6 1266.27
#Mann=3,-1,0
  4832.9    0.05       0  4997.5    0.03       0  5001.5    0.05       0
Bank Sta=4997.5,5001.5
Exp/Cntr=0.3,0.1

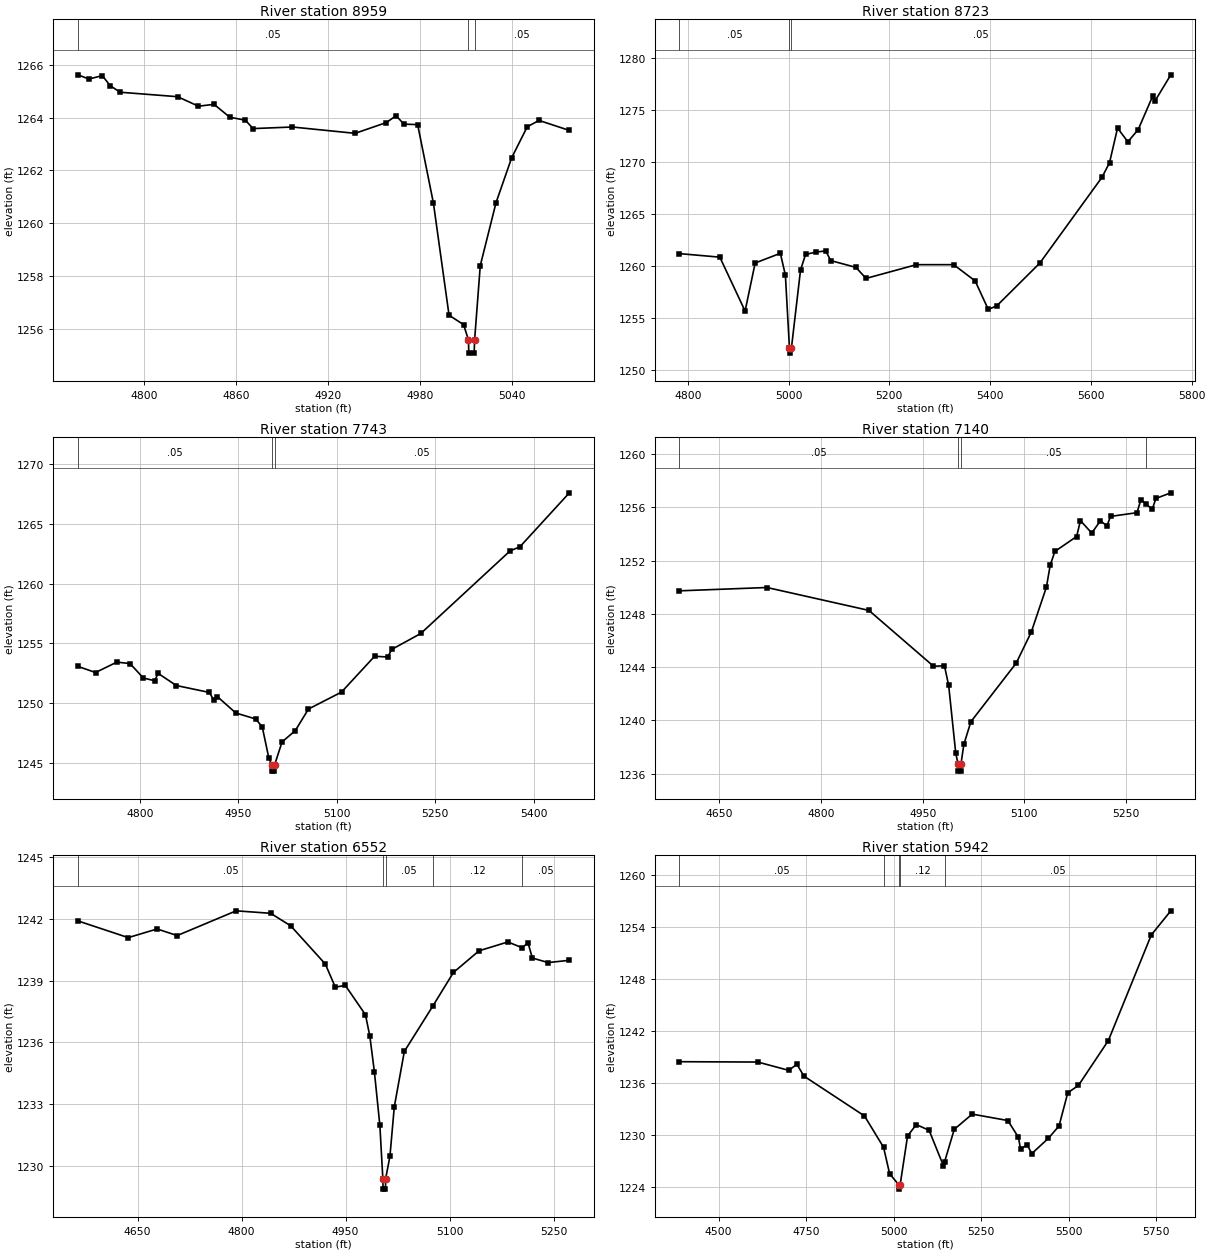
Type RM Length L Ch R = 1,8959,236,236,236
BEGIN DESCRIPTION:
LITTLE LLANO 019 12.0
END DESCRIPTION:
XS GIS Cut Line= 2
      2827928.76     10209163.99      2828242.53     10209231.75
#Sta/Elev= 30
  4756.6 1265.63  4763.7 1265.47  4772.5 1265.60  4777.6 1265.22  4784.1 1264.97
  4821.7 1264.80  4835.3 1264.44  4845.5 1264.51  4855.8 1264.02  4865.9 1263.91
  4871.0 1263.59  4896.7 1263.65  4937.6 1263.41  4958.1 1263.82  4964.4 1264.08
  4969.5 1263.76  4978.5 1263.74  4988.8 1260.76  4999.0 1256.51  5008.5 1256.15
  5011.7 1255.57  5011.9 1255.07  5015.4 1255.07  5015.7 1255.57  5019.4 1258.39
  5029.7 1260.78  5039.9 1262.48  5050.1 1263.66  5057.8 1263.90  5077.6 1263.52
#Mann=3,-1,0
  4756.6    0.05       0  5011.7    0.05       0  5015.7    0.05       0
Bank Sta=5011.7,5015.7
Exp/Cntr=0.3,0.1

Type RM Length L Ch R = 1,8723,980,980,980
BEGIN DESCRIPTION:
LITTLE LLANO 019 11.0
END DESCRIPTION:
XS GIS Cut Line= 3
      2827925.44     10209451.15      2828435.98     10209445.24
      2828888.68     10209340.64
#Sta/Elev= 30
  4783.4 1261.21  4863.6 1260.87  4913.7 1255.70  4933.7 1260.31  4983.7 1261.24
  4993.7 1259.14  5001.7 1252.16  5001.9 1251.66  5005.7 1252.16  5023.7 1259.62
  5033.7 1261.13  5053.7 1261.35  5073.7 1261.47  5083.7 1260.54  5133.7 1259.89
  5153.7 1258.83  5253.7 1260.15  5327.6 1260.15  5370.3 1258.59  5396.3 1255.86
  5413.1 1256.19  5498.6 1260.30  5622.1 1268.54  5637.0 1269.94  5652.9 1273.26
  5673.4 1271.94  5693.9 1273.12  5722.5 1276.31  5727.6 1275.89  5758.6 1278.37
#Mann=3,-1,0
  4783.4    0.05       0  5001.7    0.05       0  5005.7    0.05       0
Bank Sta=5001.7,5005.7
Exp/Cntr=0.3,0.1

Type RM Length L Ch R = 1,7743,603,603,603
BEGIN DESCRIPTION:
Mapping XS 9c0e0d2d
END DESCRIPTION:
XS GIS Cut Line= 2
      2828156.84     10210171.39      2828900.49     10210088.10
#Sta/Elev= 30
  4705.8 1253.08  4732.5 1252.57  4765.0 1253.44  4785.1 1253.32  4805.3 1252.11
  4822.7 1251.88  4827.7 1252.50  4855.6 1251.48  4905.9 1250.90  4912.9 1250.23
  4917.9 1250.56  4946.1 1249.18  4976.3 1248.68  4986.4 1248.02  4996.5 1245.39
  5001.1 1244.81  5001.4 1244.31  5004.9 1244.31  5005.1 1244.81  5016.6 1246.76
  5036.7 1247.70  5056.8 1249.51  5107.1 1250.93  5157.5 1253.93  5177.6 1253.87
  5183.5 1254.50  5227.9 1255.84  5363.9 1262.76  5378.8 1263.10  5454.1 1267.62
#Mann=3,-1,0
  4705.8    0.05       0  5001.1    0.05       0  5005.1    0.05       0
Bank Sta=5001.1,5005.1
Exp/Cntr=0.3,0.1

Type RM Length L Ch R = 1,7140,588,588,588
BEGIN DESCRIPTION:
Mapping XS 6f0bd7ca
END DESCRIPTION:
XS GIS Cut Line= 2
      2828150.89     10210874.05      2828798.43     10210547.31
#Sta/Elev= 30
  4590.9 1249.73  4720.1 1249.98  4870.6 1248.26  4965.9 1244.07  4982.1 1244.10
  4988.3 1242.63  4998.8 1237.52  5002.4 1236.69  5002.6 1236.19  5006.1 1236.19
  5006.4 1236.69  5010.7 1238.19  5021.1 1239.90  5088.0 1244.30  5110.3 1246.64
  5132.6 1250.01  5138.2 1251.66  5145.1 1252.69  5177.2 1253.81  5182.8 1255.00
  5199.5 1254.07  5212.3 1254.99  5221.8 1254.61  5227.4 1255.32  5266.4 1255.60
  5272.0 1256.58  5280.3 1256.23  5288.7 1255.85  5294.3 1256.67  5316.2 1257.09
#Mann=4,-1,0
  4590.9    0.05       0  5002.4    0.03       0  5006.4    0.05       0
  5280.3    0.12       0
Bank Sta=5002.4,5006.4
Exp/Cntr=0.3,0.1

Type RM Length L Ch R = 1,6552,610,610,610
BEGIN DESCRIPTION:
Mapping XS 58ebb572
END DESCRIPTION:
XS GIS Cut Line= 2
      2828538.01     10211386.11      2829097.75     10210951.42
#Sta/Elev= 30
  4564.0 1241.89  4636.5 1241.08  4678.1 1241.50  4707.1 1241.18  4792.1 1242.38
  4841.9 1242.26  4870.9 1241.65  4920.7 1239.80  4935.1 1238.68  4949.6 1238.76
  4978.6 1237.34  4984.9 1236.31  4991.5 1234.57  4999.4 1231.97  5003.7 1229.38
  5004.0 1228.88  5007.5 1228.88  5007.7 1229.38  5013.9 1230.47  5020.2 1232.87
  5034.7 1235.56  5075.4 1237.74  5105.5 1239.39  5142.4 1240.44  5184.0 1240.87
  5204.7 1240.59  5213.0 1240.83  5219.4 1240.09  5242.0 1239.87  5272.7 1239.98
#Mann=5,-1,0
  4564.0    0.05       0  5003.7    0.05       0  5007.7    0.05       0
  5075.4    0.12       0  5204.7    0.05       0
Bank Sta=5003.7,5007.7
Exp/Cntr=0.3,0.1

Type RM Length L Ch R = 1,5942,389,389,389
BEGIN DESCRIPTION:
Mapping XS 9d2ed369
END DESCRIPTION:
XS GIS Cut Line= 4
      2828674.97     10211600.50      2829166.76     10211517.30
      2829513.60     10211438.59      2830027.73     10211630.46
#Sta/Elev= 30
  4388.4 1238.44  4612.2 1238.40  4700.5 1237.44  4723.8 1238.14  4744.1 1236.77
  4916.8 1232.17  4971.3 1228.55  4988.6 1225.49  5014.7 1224.21  5014.9 1223.71
  5018.7 1224.21  5039.9 1229.86  5064.9 1231.17  5101.4 1230.51  5142.4 1226.40
  5145.7 1226.88  5173.2 1230.62  5224.5 1232.38  5326.2 1231.64  5356.5 1229.70
  5362.5 1228.34  5381.5 1228.84  5394.5 1227.81  5442.1 1229.59  5472.4 1231.01
  5497.4 1234.85  5527.7 1235.69  5613.3 1240.89  5736.0 1253.10  5791.6 1255.88
#Mann=5,-1,0
  4388.4    0.05       0  4971.3    0.12       0  5014.7    0.07       0
  5018.7    0.12       0  5145.7    0.05       0
Bank Sta=5014.7,5018.7
Exp/Cntr=0.3,0.1

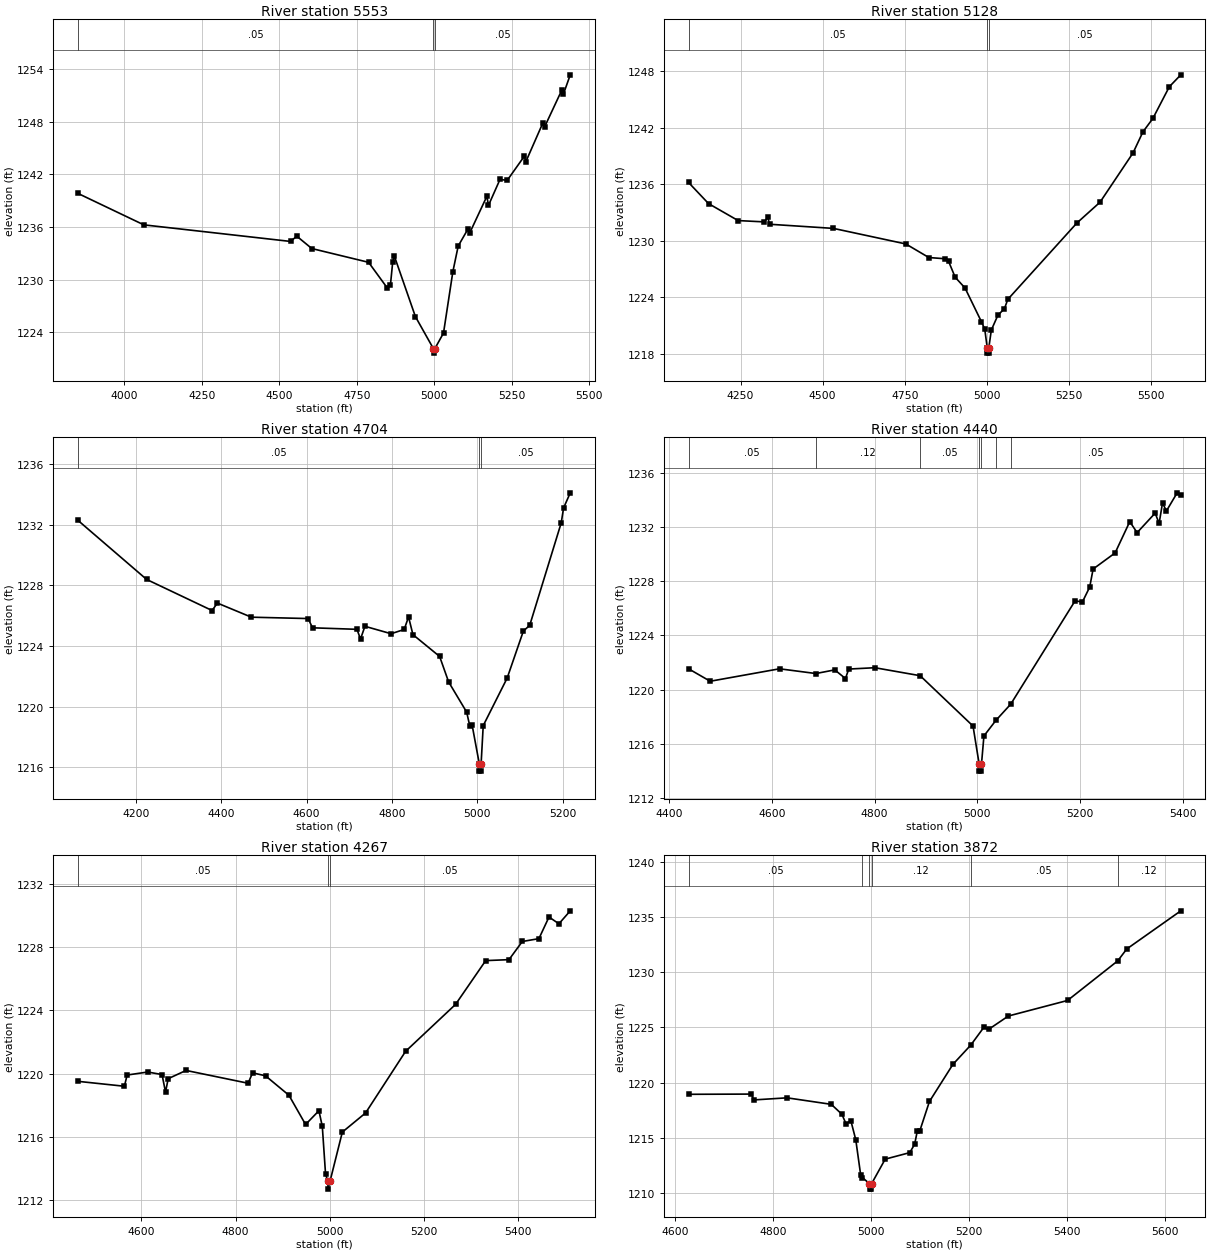
Type RM Length L Ch R = 1,5553,425,425,425
BEGIN DESCRIPTION:
LITTLE LLANO 019 9.0
END DESCRIPTION:
XS GIS Cut Line= 3
      2828364.87     10211935.47      2829584.79     10211793.79
      2829939.12     10211733.77
#Sta/Elev= 30
  3851.2 1239.84  4063.4 1236.26  4536.6 1234.37  4556.7 1234.97  4605.2 1233.56
  4788.3 1231.99  4848.7 1229.06  4858.7 1229.39  4866.1 1232.04  4871.2 1232.72
  4939.3 1225.80  4997.5 1222.14  4997.8 1221.64  5001.8 1222.14  5029.9 1223.93
  5060.1 1230.93  5077.3 1233.85  5109.5 1235.83  5114.5 1235.34  5169.8 1239.52
  5174.9 1238.48  5212.1 1241.44  5235.3 1241.33  5290.5 1244.08  5295.6 1243.47
  5350.9 1247.92  5356.0 1247.43  5411.3 1251.61  5416.3 1251.13  5438.7 1253.36
#Mann=3,-1,0
  3851.2    0.05       0  4997.5    0.05       0  5001.8    0.05       0
Bank Sta=4997.5,5001.8
Exp/Cntr=0.3,0.1

Type RM Length L Ch R = 1,5128,424,424,424
BEGIN DESCRIPTION:
LITTLE LLANO 019 8.0
END DESCRIPTION:
XS GIS Cut Line= 3
      2828595.00     10212270.22      2829658.37     10212218.10
      2830090.43     10212176.59
#Sta/Elev= 30
  4091.7 1236.18  4152.5 1233.94  4242.6 1232.14  4322.7 1232.00  4332.7 1232.50
  4338.4 1231.75  4532.9 1231.31  4753.2 1229.66  4823.3 1228.22  4873.3 1228.09
  4883.3 1227.82  4903.4 1226.13  4933.4 1224.99  4983.5 1221.40  4993.5 1220.62
  5001.3 1218.58  5001.6 1218.08  5005.3 1218.08  5005.6 1218.58  5013.5 1220.53
  5033.5 1222.10  5053.5 1222.80  5063.6 1223.78  5274.2 1231.89  5344.5 1234.09
  5445.0 1239.32  5475.1 1241.55  5505.3 1242.97  5555.5 1246.34  5590.4 1247.60
#Mann=3,-1,0
  4091.7    0.05       0  5001.3    0.03       0  5005.6    0.05       0
Bank Sta=5001.3,5005.6
Exp/Cntr=0.3,0.1

Type RM Length L Ch R = 1,4704,264,264,264
BEGIN DESCRIPTION:
LITTLE LLANO 019 7.0
END DESCRIPTION:
XS GIS Cut Line= 3
      2828688.66     10212837.56      2829478.43     10212664.25
      2829805.71     10212553.10
#Sta/Elev= 30
  4064.0 1232.27  4224.8 1228.38  4378.3 1226.33  4390.8 1226.82  4470.5 1225.89
  4603.6 1225.80  4613.8 1225.19  4718.0 1225.09  4726.4 1224.45  4736.7 1225.29
  4798.1 1224.80  4828.8 1225.08  4839.0 1225.91  4849.3 1224.74  4911.9 1223.30
  4933.0 1221.62  4975.3 1219.63  4982.8 1218.69  4988.0 1218.79  5004.8 1216.24
  5005.1 1215.74  5008.9 1215.74  5009.2 1216.24  5014.1 1218.74  5070.3 1221.88
  5108.3 1224.98  5123.1 1225.35  5197.1 1232.12  5202.5 1233.09  5218.2 1234.09
#Mann=3,-1,0
  4064.0    0.05       0  5004.8    0.05       0  5009.2    0.05       0
Bank Sta=5004.8,5009.2
Exp/Cntr=0.3,0.1

Type RM Length L Ch R = 1,4440,173,173,173
BEGIN DESCRIPTION:
LITTLE LLANO 019 6.0
END DESCRIPTION:
XS GIS Cut Line= 3
      2829270.70     10213216.58      2829529.21     10213014.10
      2830005.68     10212603.12
#Sta/Elev= 30
  4438.2 1221.54  4480.3 1220.62  4615.1 1221.54  4685.9 1221.19  4722.6 1221.46
  4743.4 1220.82  4749.8 1221.52  4800.6 1221.62  4888.7 1221.03  4991.6 1217.31
  5003.6 1214.48  5003.9 1213.98  5007.7 1213.98  5008.0 1214.48  5012.8 1216.58
  5036.1 1217.73  5065.0 1218.93  5190.1 1226.56  5204.4 1226.48  5218.6 1227.58
  5225.2 1228.91  5268.0 1230.10  5296.5 1232.41  5310.8 1231.60  5345.9 1233.04
  5353.6 1232.28  5360.2 1233.79  5367.8 1233.20  5388.7 1234.54  5395.8 1234.35
#Mann=7,-1,0
  4438.2    0.05       0  4685.9    0.12       0  4888.7    0.05       0
  5003.6    0.05       0  5008.0    0.05       0  5036.1    0.12       0
  5065.0    0.05       0
Bank Sta=5003.6,5008
Exp/Cntr=0.3,0.1

Type RM Length L Ch R = 1,4267,395,395,395
BEGIN DESCRIPTION:
LITTLE LLANO 019 5.0
END DESCRIPTION:
XS GIS Cut Line= 3
      2829349.51     10213308.37      2829680.73     10213126.24
      2830140.95     10212644.55
#Sta/Elev= 30
  4465.8 1219.51  4564.1 1219.20  4570.0 1219.91  4613.6 1220.10  4644.0 1219.94
  4651.4 1218.83  4657.1 1219.68  4695.0 1220.20  4826.6 1219.39  4836.1 1220.05
  4863.5 1219.86  4913.2 1218.63  4948.5 1216.78  4976.8 1217.65  4984.0 1216.66
  4990.9 1213.63  4995.8 1213.19  4996.1 1212.69  5000.4 1213.19  5026.5 1216.30
  5075.8 1217.51  5160.7 1221.41  5266.7 1224.38  5330.6 1227.15  5380.0 1227.21
  5408.3 1228.36  5443.5 1228.54  5464.9 1229.91  5485.9 1229.48  5510.0 1230.30
#Mann=3,-1,0
  4465.8    0.05       0  4995.8    0.05       0  5000.4    0.05       0
Bank Sta=4995.8,5000.4
Exp/Cntr=0.3,0.1

Type RM Length L Ch R = 1,3872,203,203,203
BEGIN DESCRIPTION:
Mapping XS dcfceb58
END DESCRIPTION:
XS GIS Cut Line= 3
      2829354.87     10213340.85      2829821.42     10213366.89
      2830355.25     10213303.96
#Sta/Elev= 30
  4627.3 1218.94  4755.4 1218.96  4760.4 1218.43  4828.4 1218.62  4918.6 1218.03
  4940.3 1217.13  4948.6 1216.27  4958.6 1216.54  4968.6 1214.82  4978.7 1211.60
  4982.2 1211.39  4996.4 1210.84  4996.7 1210.34  5000.7 1210.34  5001.0 1210.84
  5028.7 1213.06  5078.8 1213.65  5088.8 1214.41  5094.2 1215.61  5099.2 1215.61
  5119.0 1218.29  5167.0 1221.66  5203.5 1223.41  5229.8 1225.00  5239.8 1224.83
  5280.1 1226.04  5400.9 1227.45  5503.3 1231.04  5521.8 1232.12  5632.1 1235.58
#Mann=6,-1,0
  4627.3    0.05       0  4982.2    0.12       0  4996.4    0.07       0
  5001.0    0.12       0  5203.5    0.05       0  5503.3    0.12       0
Bank Sta=4996.4,5001
Exp/Cntr=0.3,0.1