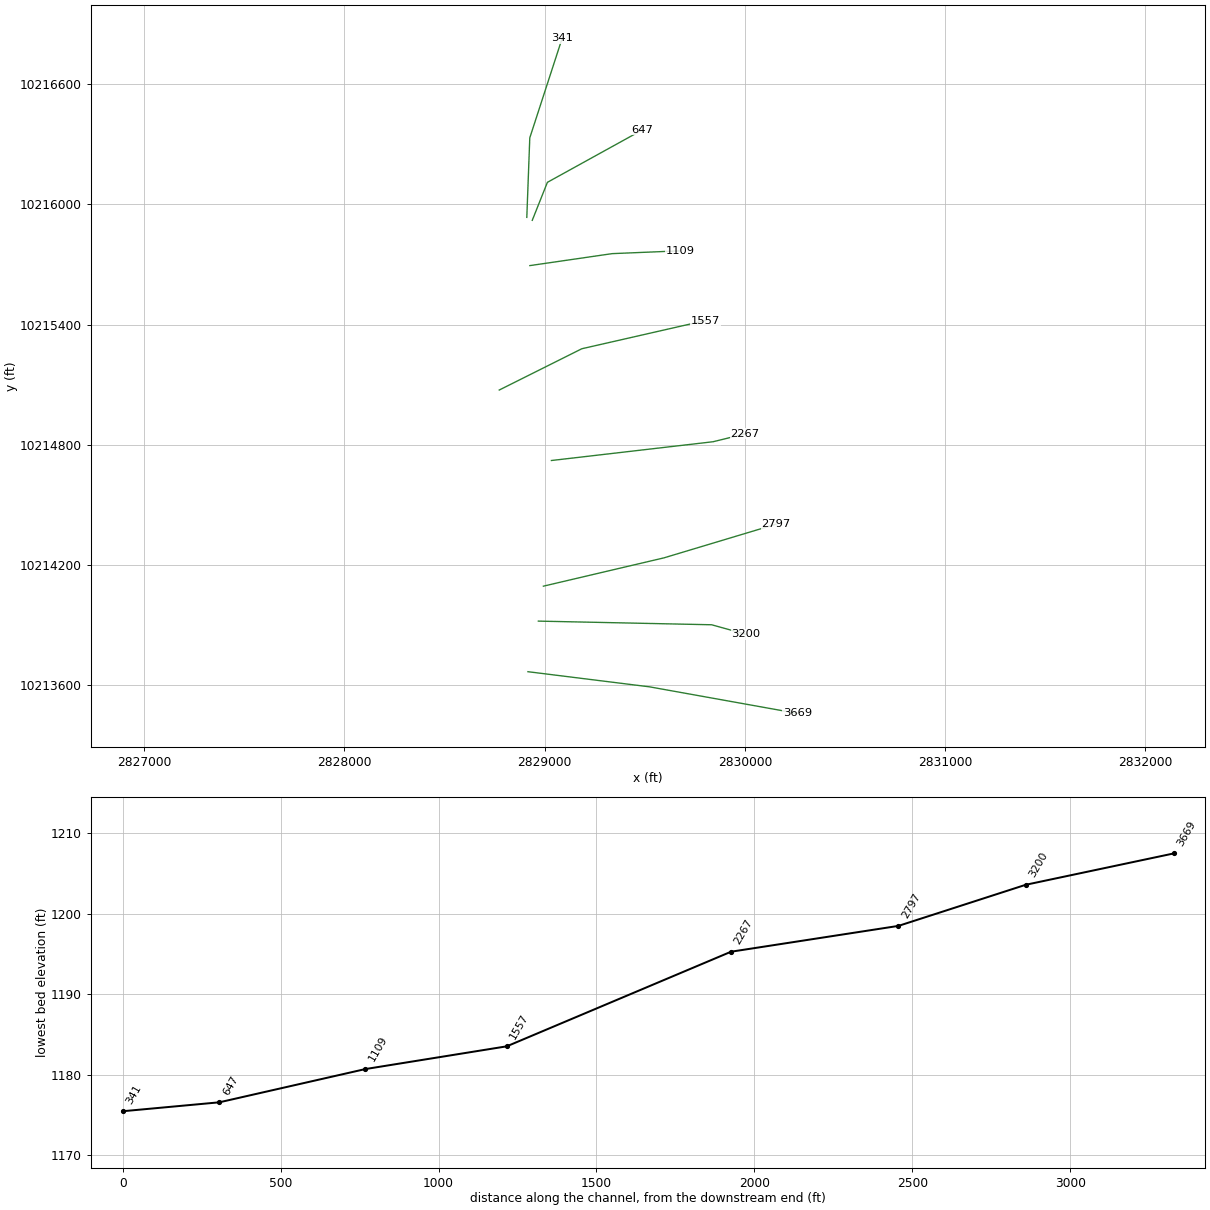
HEC-RAS study LITTLE LLANO 019.prj: LITTLE LLANO 019 Base Level Engineering

--- LITTLE LLANO 019.g01 (geometry) --- (continued)

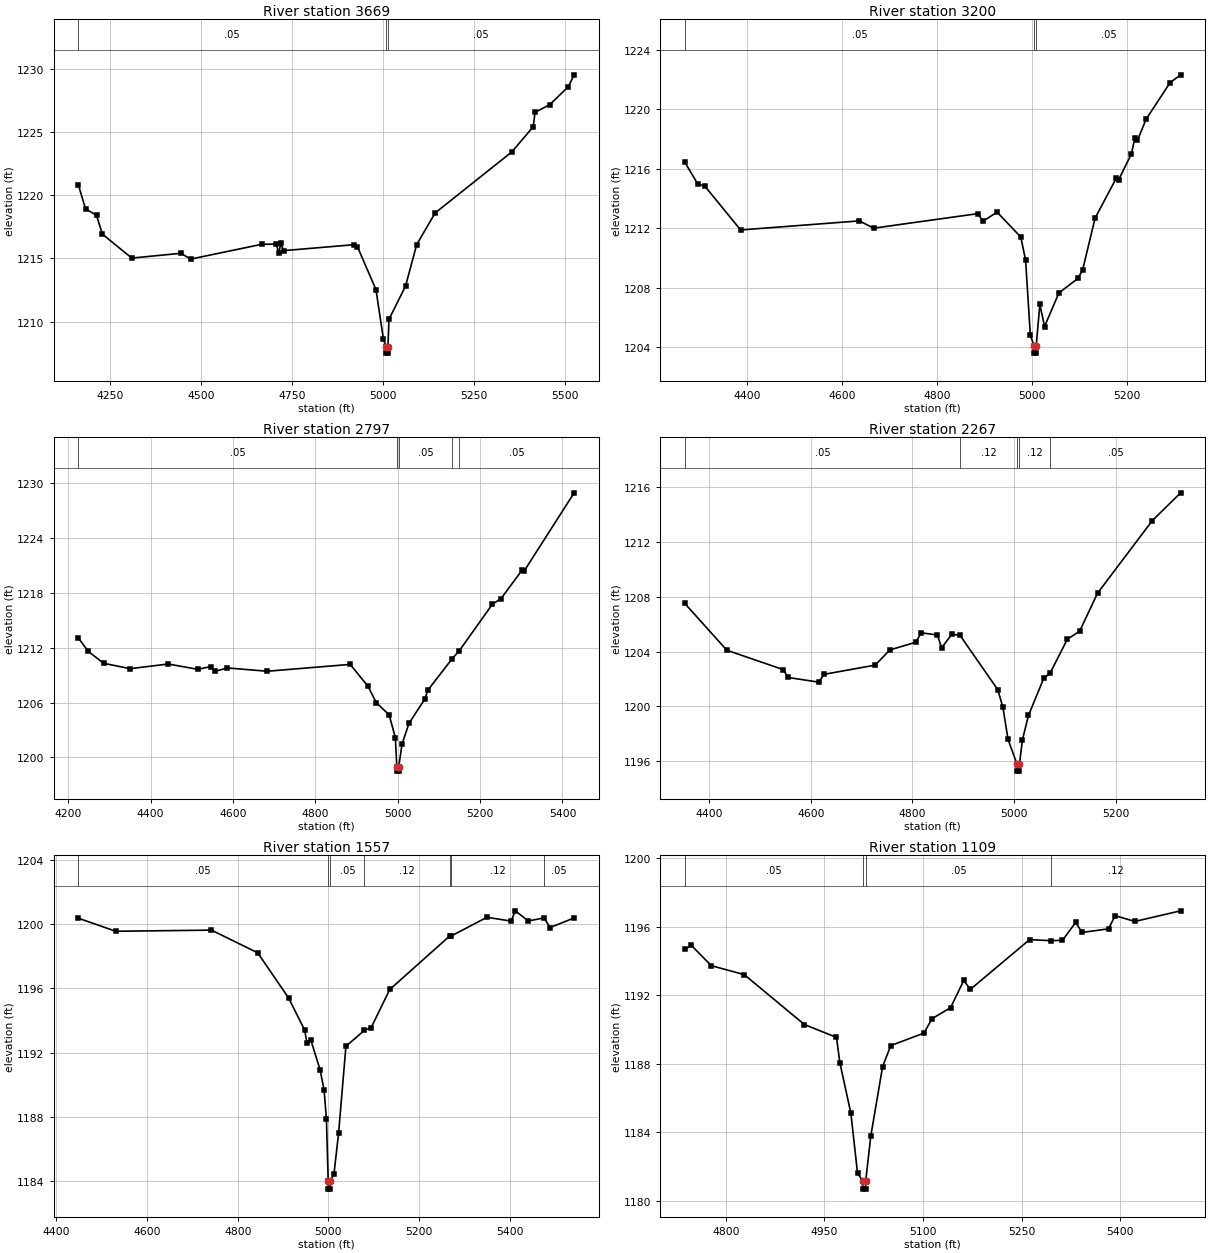
Type RM Length L Ch R = 1,3669,469,469,469
BEGIN DESCRIPTION:
Mapping XS 94536284
END DESCRIPTION:
XS GIS Cut Line= 3
      2828916.10     10213666.37      2829522.85     10213590.85
      2830261.41     10213458.23
#Sta/Elev= 30
  4162.8 1220.84  4182.5 1218.94  4212.8 1218.41  4228.8 1216.93  4309.6 1215.03
  4444.5 1215.41  4471.2 1214.95  4666.2 1216.12  4706.5 1216.14  4713.5 1215.41
  4718.6 1216.20  4726.7 1215.62  4919.3 1216.09  4929.5 1215.92  4980.3 1212.53
  5000.6 1208.64  5008.5 1208.00  5008.8 1207.50  5012.8 1207.50  5013.1 1208.00
  5016.0 1210.18  5061.6 1212.82  5092.1 1216.10  5142.9 1218.61  5353.3 1223.44
  5412.1 1225.43  5417.2 1226.58  5457.8 1227.19  5508.6 1228.61  5524.6 1229.55
#Mann=3,-1,0
  4162.8    0.05       0  5008.5    0.03       0  5013.1    0.05       0
Bank Sta=5008.5,5013.1
Exp/Cntr=0.3,0.1

Type RM Length L Ch R = 1,3200,403,403,403
BEGIN DESCRIPTION:
LITTLE LLANO 019 4.0
END DESCRIPTION:
XS GIS Cut Line= 3
      2828968.13     10213918.98      2829833.36     10213900.75
      2830005.67     10213853.11
#Sta/Elev= 30
  4269.0 1216.44  4296.6 1214.95  4310.9 1214.84  4386.6 1211.88  4636.6 1212.49
  4666.6 1212.00  4886.7 1212.98  4896.7 1212.46  4926.7 1213.08  4976.7 1211.40
  4986.7 1209.84  4996.7 1204.81  5004.4 1204.10  5004.7 1203.60  5008.7 1203.60
  5009.1 1204.10  5016.7 1206.87  5026.7 1205.39  5056.7 1207.64  5096.7 1208.62
  5106.7 1209.18  5133.1 1212.68  5177.5 1215.35  5182.7 1215.26  5209.5 1216.99
  5217.0 1218.09  5222.2 1217.90  5240.6 1219.33  5290.9 1221.78  5313.2 1222.31
#Mann=3,-1,0
  4269.0    0.05       0  5004.4    0.05       0  5009.1    0.05       0
Bank Sta=5004.4,5009.1
Exp/Cntr=0.3,0.1

Type RM Length L Ch R = 1,2797,530,530,530
BEGIN DESCRIPTION:
LITTLE LLANO 019 3.0
END DESCRIPTION:
XS GIS Cut Line= 3
      2828993.32     10214093.46      2829595.73     10214234.95
      2830155.72     10214403.12
#Sta/Elev= 30
  4224.8 1213.08  4249.0 1211.60  4286.3 1210.30  4350.5 1209.71  4442.9 1210.22
  4514.8 1209.64  4545.7 1209.94  4556.2 1209.41  4586.7 1209.79  4683.4 1209.43
  4884.7 1210.18  4928.2 1207.76  4948.0 1205.99  4979.3 1204.65  4994.3 1202.14
  4997.8 1198.99  4998.2 1198.49  5002.2 1198.49  5002.5 1198.99  5010.6 1201.47
  5027.4 1203.72  5065.6 1206.37  5073.3 1207.36  5132.5 1210.82  5148.6 1211.62
  5229.9 1216.77  5250.8 1217.39  5302.2 1220.52  5307.4 1220.44  5428.3 1228.97
#Mann=5,-1,0
  4224.8    0.05       0  4997.8    0.03       0  5002.5    0.05       0
  5132.5    0.12       0  5148.6    0.05       0
Bank Sta=4997.8,5002.5
Exp/Cntr=0.3,0.1

Type RM Length L Ch R = 1,2267,710,710,710
BEGIN DESCRIPTION:
Mapping XS f762c7cd
END DESCRIPTION:
XS GIS Cut Line= 3
      2829033.50     10214721.06      2829840.78     10214814.81
      2829999.65     10214853.88
#Sta/Elev= 30
  4351.8 1207.51  4434.5 1204.10  4545.3 1202.69  4555.3 1202.11  4615.7 1201.77
  4625.8 1202.34  4726.5 1203.01  4755.7 1204.12  4807.0 1204.69  4817.1 1205.37
  4849.3 1205.21  4857.4 1204.27  4877.5 1205.26  4893.6 1205.19  4968.1 1201.22
  4978.2 1199.93  4988.2 1197.61  5006.0 1195.78  5006.3 1195.28  5010.4 1195.28
  5010.7 1195.78  5016.6 1197.56  5028.5 1199.34  5058.7 1202.06  5071.1 1202.43
  5105.2 1204.91  5129.2 1205.48  5164.5 1208.26  5272.5 1213.56  5328.1 1215.58
#Mann=5,-1,0
  4351.8    0.05       0  4893.6    0.12       0  5006.0    0.07       0
  5010.7    0.12       0  5071.1    0.05       0
Bank Sta=5006,5010.7
Exp/Cntr=0.3,0.1

Type RM Length L Ch R = 1,1557,448,448,448
BEGIN DESCRIPTION:
Mapping XS a0cd583a
END DESCRIPTION:
XS GIS Cut Line= 3
      2828773.01     10215073.05      2829185.34     10215279.22
      2829802.30     10215419.93
#Sta/Elev= 30
  4448.3 1200.36  4530.9 1199.55  4742.0 1199.62  4844.0 1198.21  4912.0 1195.41
  4947.4 1193.42  4952.6 1192.63  4960.9 1192.81  4981.5 1190.95  4990.4 1189.69
  4995.6 1187.87  4999.5 1184.02  4999.9 1183.52  5004.1 1183.52  5004.4 1184.02
  5012.2 1184.45  5022.5 1187.02  5038.6 1192.40  5079.4 1193.39  5094.3 1193.56
  5135.3 1195.93  5267.3 1199.25  5270.4 1199.25  5349.8 1200.42  5403.1 1200.18
  5412.2 1200.82  5440.9 1200.19  5475.8 1200.38  5489.1 1199.78  5542.1 1200.38
#Mann=7,-1,0
  4448.3    0.05       0  4999.5    0.05       0  5004.4    0.05       0
  5079.4    0.12       0  5267.3    0.05       0  5270.4    0.12       0
  5475.8    0.05       0
Bank Sta=4999.5,5004.4
Exp/Cntr=0.3,0.1

Type RM Length L Ch R = 1,1109,462,462,462
BEGIN DESCRIPTION:
LITTLE LLANO 019 2.0
END DESCRIPTION:
XS GIS Cut Line= 3
      2828925.73     10215694.44      2829337.00     10215754.21
      2829675.22     10215768.17
#Sta/Elev= 30
  4737.8 1194.67  4747.9 1194.90  4778.2 1193.72  4828.2 1193.20  4919.6 1190.29
  4968.5 1189.54  4973.6 1188.07  4990.4 1185.11  5000.5 1181.62  5008.1 1181.19
  5008.5 1180.69  5012.7 1180.69  5013.0 1181.19  5020.7 1183.79  5038.6 1187.83
  5051.0 1189.06  5101.5 1189.79  5113.8 1190.63  5142.0 1191.27  5162.1 1192.86
  5172.1 1192.34  5262.2 1195.24  5294.8 1195.18  5312.2 1195.20  5332.2 1196.24
  5342.2 1195.66  5382.3 1195.87  5392.3 1196.64  5422.3 1196.30  5491.9 1196.92
#Mann=4,-1,0
  4737.8    0.05       0  5008.1    0.05       0  5013.0    0.05       0
  5294.8    0.12       0
Bank Sta=5008.1,5013
Exp/Cntr=0.3,0.1

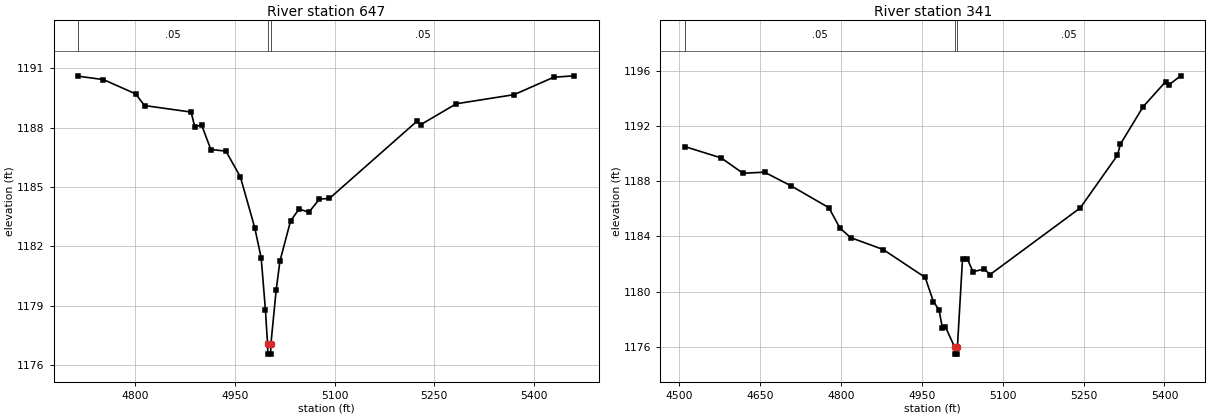
Type RM Length L Ch R = 1,647,306,306,306
BEGIN DESCRIPTION:
Mapping XS 62326e7d
END DESCRIPTION:
XS GIS Cut Line= 3
      2828937.72     10215920.50      2829013.32     10216110.27
      2829488.47     10216372.53
#Sta/Elev= 30
  4713.9 1190.59  4751.7 1190.42  4800.2 1189.70  4813.6 1189.11  4883.8 1188.78
  4889.2 1188.05  4899.7 1188.12  4913.5 1186.89  4936.2 1186.81  4958.0 1185.51
  4979.7 1182.94  4989.4 1181.41  4995.8 1178.78  4999.0 1177.06  4999.4 1176.56
  5003.6 1176.56  5004.0 1177.06  5011.9 1179.78  5017.6 1181.25  5033.6 1183.28
  5046.5 1183.89  5061.1 1183.72  5077.2 1184.39  5092.2 1184.42  5223.8 1188.31
  5229.5 1188.14  5283.4 1189.20  5370.5 1189.66  5430.1 1190.54  5460.9 1190.61
#Mann=3,-1,0
  4713.9    0.05       0  4999.0    0.05       0  5004.0    0.05       0
Bank Sta=4999,5004
Exp/Cntr=0.3,0.1

Type RM Length L Ch R = 1,341,0,0,0
BEGIN DESCRIPTION:
LITTLE LLANO 019 1.0
END DESCRIPTION:
XS GIS Cut Line= 3
      2828910.51     10215935.31      2828925.39     10216332.41
      2829086.96     10216829.43
#Sta/Elev= 30
  4510.0 1190.53  4577.8 1189.70  4617.9 1188.59  4657.9 1188.67  4707.9 1187.66
  4777.3 1186.09  4798.0 1184.60  4818.0 1183.91  4878.1 1183.05  4956.1 1181.02
  4971.2 1179.27  4981.7 1178.66  4988.1 1177.34  4993.3 1177.45  5010.8 1175.95
  5011.1 1175.45  5015.4 1175.45  5015.8 1175.95  5025.3 1182.36  5034.3 1182.35
  5044.8 1181.44  5065.8 1181.63  5076.4 1181.23  5243.7 1186.07  5312.8 1189.90
  5318.2 1190.70  5360.3 1193.42  5402.3 1195.25  5408.6 1195.02  5430.0 1195.67
#Mann=3,-1,0
  4510.0    0.05       0  5010.8    0.05       0  5015.8    0.05       0
Bank Sta=5010.8,5015.8
Exp/Cntr=0.3,0.1

Chan Stop Cuts=-1