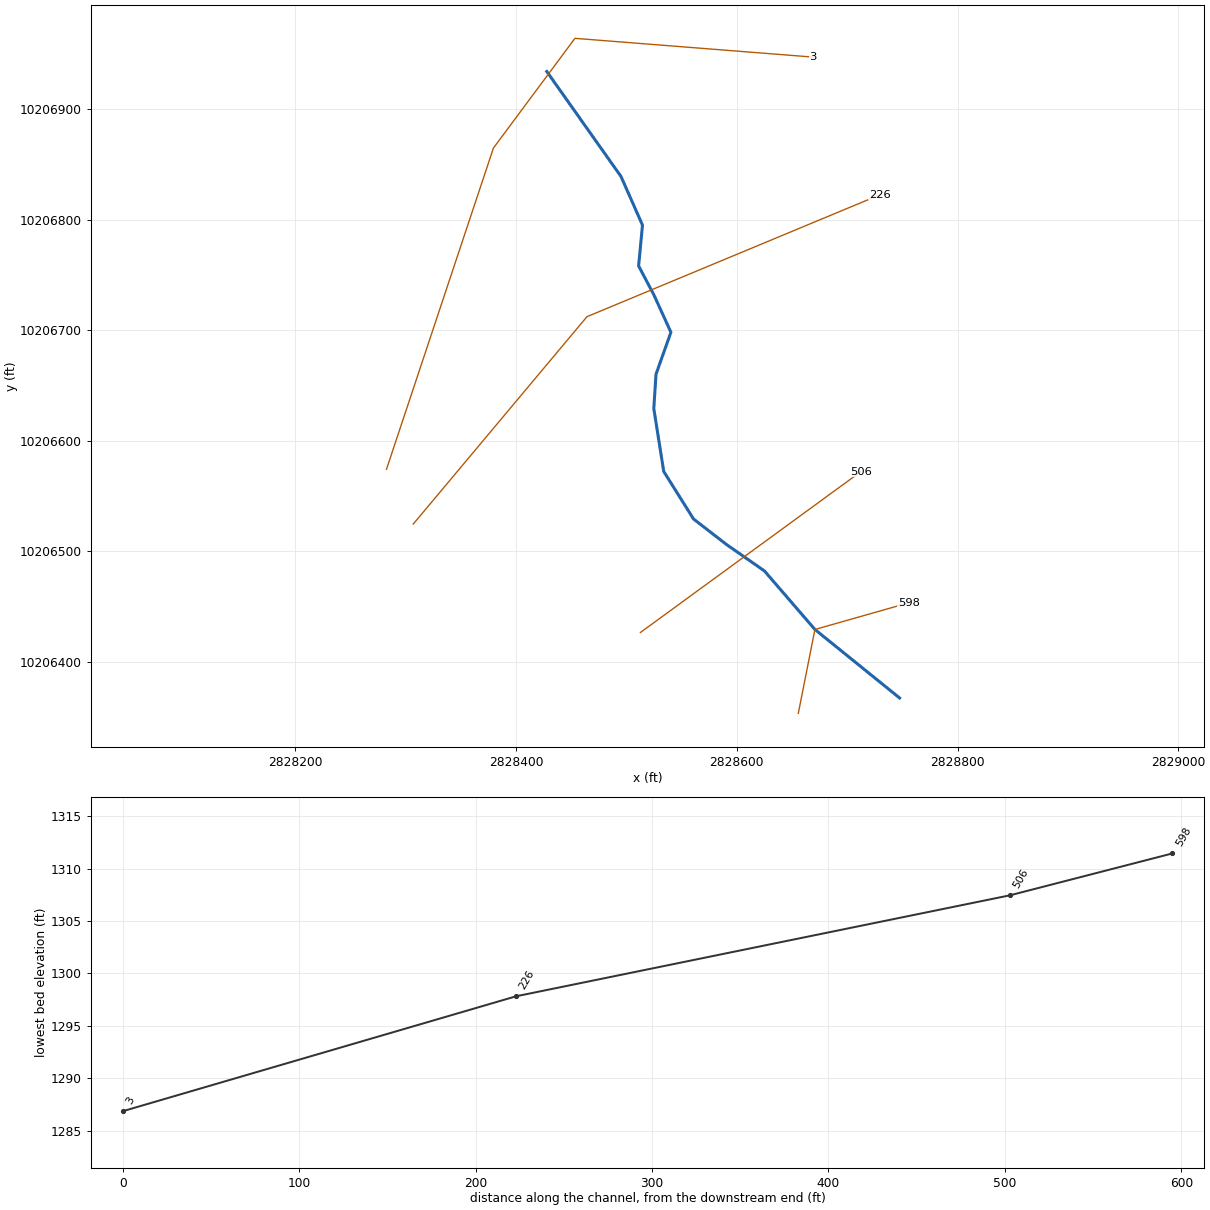
--- LITTLE LLANO 020.prj (project) ---

Proj Title=LITTLE LLANO 020 Base Level Engineering
Current Plan=p01
Default Exp/Contr=0.3,0.1
English Units
Geom File=g01
Flow File=f01
Plan File=p01
BEGIN DESCRIPTION:
LITTLE LLANO 020
END DESCRIPTION:

--- LITTLE LLANO 020.p01 (plan) ---

Plan Title=Multiple Run
Short Identifier=Multiple
Geom File=g01
Flow File=f01
Subcritical Flow
K Sum by GR= 0
Std Step Tol= 0.01
Critical Tol= 0.01
Num of Std Step Trials= 20
Max Error Tol= 0.3
Flow Tol Ratio= 0.001
Split Flow NTrial= 30
Split Flow Tol= 0.02
Split Flow Ratio= 0.02
Log Output Level= 0
Friction Slope Method= 1
Unsteady Friction Slope Method= 2
Unsteady Bridges Friction Slope Method= 1
Parabolic Critical Depth
Global Vel Dist=  1 , 1 , 1
Global Log Level= 0
CheckData=True
Encroach Param= -1, 0, 0, 0
BEGIN DESCRIPTION:
Multiple Run
END DESCRIPTION:

--- LITTLE LLANO 020.f01 (steady flow) ---

Flow Title=Multiple
Number of Profiles=7
Profile Names=10-year,25-year,50-year,1pct_min,100-year,1pct_plu,500-year
River Rch & RM= LITTLE LLANO 020,Reach-1,598
      56      80     189     195     256     337     395
River Rch & RM= LITTLE LLANO 020,Reach-1,3
     412     667    1414    1114    2000    3589    2943
Boundary for River Rch & Prof#=LITTLE LLANO 020,Reach-1,1
Up Type=0
Dn Type=3
Dn Slope=0.005
Boundary for River Rch & Prof#=LITTLE LLANO 020,Reach-1,2
Up Type=0
Dn Type=3
Dn Slope=0.005
Boundary for River Rch & Prof#=LITTLE LLANO 020,Reach-1,3
Up Type=0
Dn Type=3
Dn Slope=0.005
Boundary for River Rch & Prof#=LITTLE LLANO 020,Reach-1,4
Up Type=0
Dn Type=3
Dn Slope=0.005
Boundary for River Rch & Prof#=LITTLE LLANO 020,Reach-1,5
Up Type=0
Dn Type=3
Dn Slope=0.005
Boundary for River Rch & Prof#=LITTLE LLANO 020,Reach-1,6
Up Type=0
Dn Type=3
Dn Slope=0.005
Boundary for River Rch & Prof#=LITTLE LLANO 020,Reach-1,7
Up Type=0
Dn Type=3
Dn Slope=0.005

--- LITTLE LLANO 020.g01 (geometry) ---

Geom Title=Existing Conditions

River Reach=LITTLE LLANO 020,Reach-1
Reach XY= 14
      2828747.50     10206367.00      2828670.75     10206429.00
      2828625.00     10206482.00      2828590.50     10206506.00
      2828560.75     10206529.00      2828533.75     10206572.00
      2828524.75     10206629.00      2828526.75     10206660.00
      2828540.25     10206698.00      2828524.75     10206732.00
      2828511.00     10206758.00      2828514.50     10206795.00
      2828495.00     10206839.00      2828427.75     10206934.00

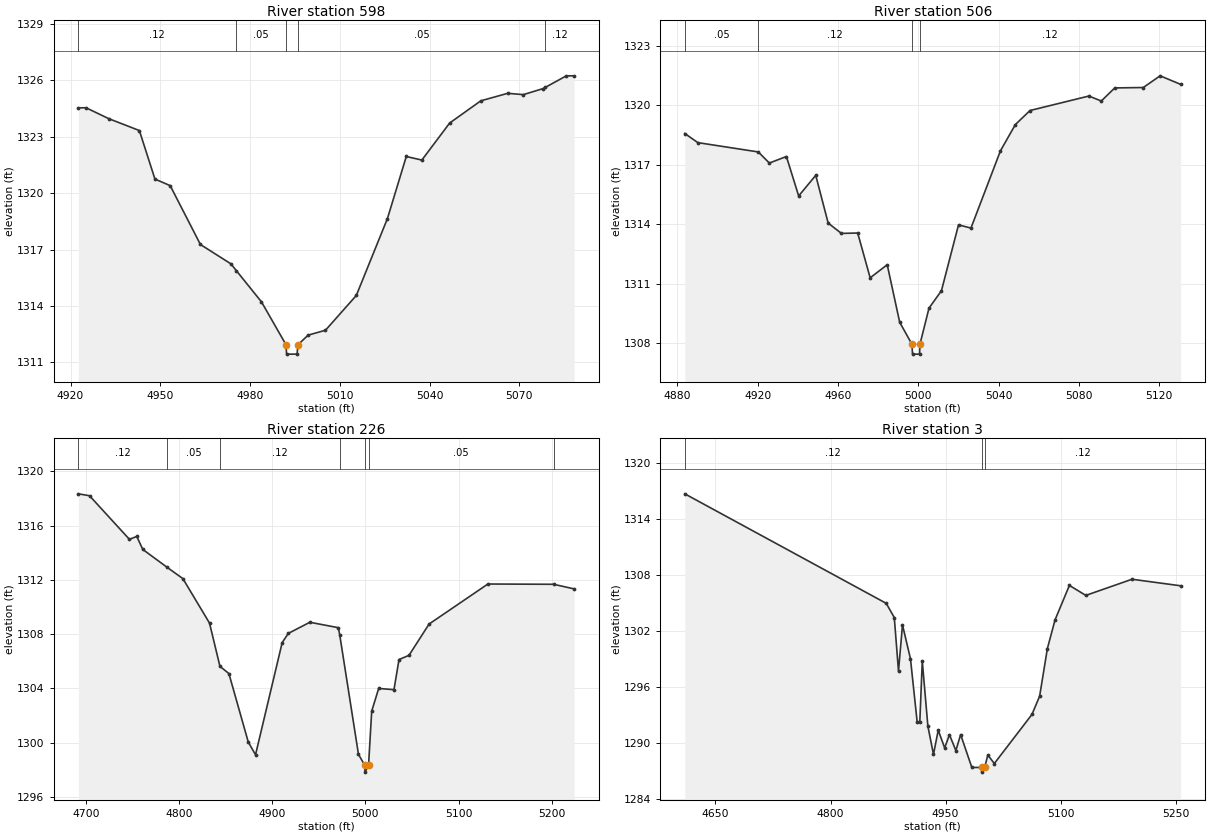
Type RM Length L Ch R = 1,598,92,92,92
BEGIN DESCRIPTION:
LITTLE LLANO 020 1.0
END DESCRIPTION:
XS GIS Cut Line= 3
      2828655.68     10206353.08      2828670.75     10206429.00
      2828755.69     10206453.11
#Sta/Elev= 28
  4922.6 1324.54  4925.2 1324.54  4932.8 1323.96  4943.0 1323.33  4948.2 1320.75
  4953.3 1320.40  4963.4 1317.27  4973.6 1316.24  4975.4 1315.88  4983.8 1314.22
  4992.0 1311.94  4992.2 1311.44  4995.7 1311.44  4996.0 1311.94  4999.4 1312.45
  5005.2 1312.71  5015.5 1314.56  5025.9 1318.65  5032.2 1321.95  5037.4 1321.76
  5046.7 1323.73  5057.1 1324.91  5066.1 1325.31  5071.3 1325.24  5077.9 1325.56
  5078.7 1325.63  5085.7 1326.24  5088.3 1326.24
#Mann=5,-1,0
  4922.6    0.12       0  4975.4    0.05       0  4992.0    0.05       0
  4996.0    0.05       0  5078.7    0.12       0
Bank Sta=4992,4996
Exp/Cntr=0.3,0.1

Type RM Length L Ch R = 1,506,280,280,280
BEGIN DESCRIPTION:
Mapping XS c1bed7fe
END DESCRIPTION:
XS GIS Cut Line= 2
      2828512.64     10206426.28      2828712.16     10206571.71
#Sta/Elev= 30
  4883.7 1318.58  4890.2 1318.12  4920.3 1317.65  4925.8 1317.09  4934.3 1317.42
  4940.4 1315.43  4948.9 1316.47  4955.1 1314.06  4961.7 1313.54  4969.8 1313.56
  4976.0 1311.30  4984.5 1311.96  4990.7 1309.06  4996.8 1307.95  4997.1 1307.45
  5000.6 1307.45  5000.8 1307.95  5005.3 1309.77  5011.5 1310.65  5020.0 1313.97
  5026.2 1313.81  5040.9 1317.71  5048.3 1319.03  5055.6 1319.74  5084.9 1320.47
  5091.1 1320.22  5097.8 1320.88  5112.0 1320.90  5120.4 1321.49  5130.6 1321.06
#Mann=4,-1,0
  4883.7    0.05       0  4920.3    0.12       0  4996.8    0.07       0
  5000.8    0.12       0
Bank Sta=4996.8,5000.8
Exp/Cntr=0.3,0.1

Type RM Length L Ch R = 1,226,223,223,223
BEGIN DESCRIPTION:
Mapping XS edbae397
END DESCRIPTION:
XS GIS Cut Line= 3
      2828306.76     10206524.38      2828464.19     10206712.08
      2828729.42     10206822.29
#Sta/Elev= 30
  4691.9 1318.34  4703.9 1318.20  4746.8 1314.98  4754.6 1315.20  4761.1 1314.24
  4787.4 1312.91  4804.1 1312.09  4832.7 1308.81  4843.9 1305.62  4853.5 1305.09
  4874.3 1300.04  4882.1 1299.10  4910.7 1307.37  4917.3 1308.05  4940.4 1308.87
  4971.0 1308.47  4972.5 1307.93  4992.6 1299.13  4999.4 1298.32  4999.6 1297.82
  5003.4 1298.32  5006.8 1302.32  5014.3 1303.99  5030.7 1303.90  5036.1 1306.12
  5046.8 1306.43  5068.4 1308.74  5131.5 1311.69  5202.0 1311.67  5224.1 1311.33
#Mann=7,-1,0
  4691.9    0.12       0  4787.4    0.05       0  4843.9    0.12       0
  4972.5    0.05       0  4999.4    0.05       0  5003.4    0.05       0
  5202.0    0.12       0
Bank Sta=4999.4,5003.4
Exp/Cntr=0.3,0.1

Type RM Length L Ch R = 1,3,0,0,0
BEGIN DESCRIPTION:
LITTLE LLANO 020 2.0
END DESCRIPTION:
XS GIS Cut Line= 4
      2828282.53     10206574.03      2828379.41     10206864.68
      2828453.29     10206963.99      2828668.87     10206947.03
#Sta/Elev= 30
  4610.0 1316.67  4872.6 1304.94  4883.1 1303.42  4888.6 1297.68  4893.8 1302.63
  4904.2 1299.00  4912.9 1292.26  4916.4 1292.26  4919.6 1298.75  4926.9 1291.78
  4934.2 1288.76  4940.4 1291.35  4948.8 1289.45  4955.0 1290.87  4963.4 1289.17
  4969.6 1290.88  4984.2 1287.36  4996.9 1287.36  4997.1 1286.86  5000.9 1287.36
  5005.1 1288.69  5013.5 1287.78  5062.6 1293.04  5072.6 1295.00  5082.7 1300.10
  5092.7 1303.17  5111.4 1306.86  5132.8 1305.79  5193.0 1307.52  5256.4 1306.82
#Mann=3,-1,0
  4610.0    0.12       0  4996.9    0.07       0  5000.9    0.12       0
Bank Sta=4996.9,5000.9
Exp/Cntr=0.3,0.1

Chan Stop Cuts=-1