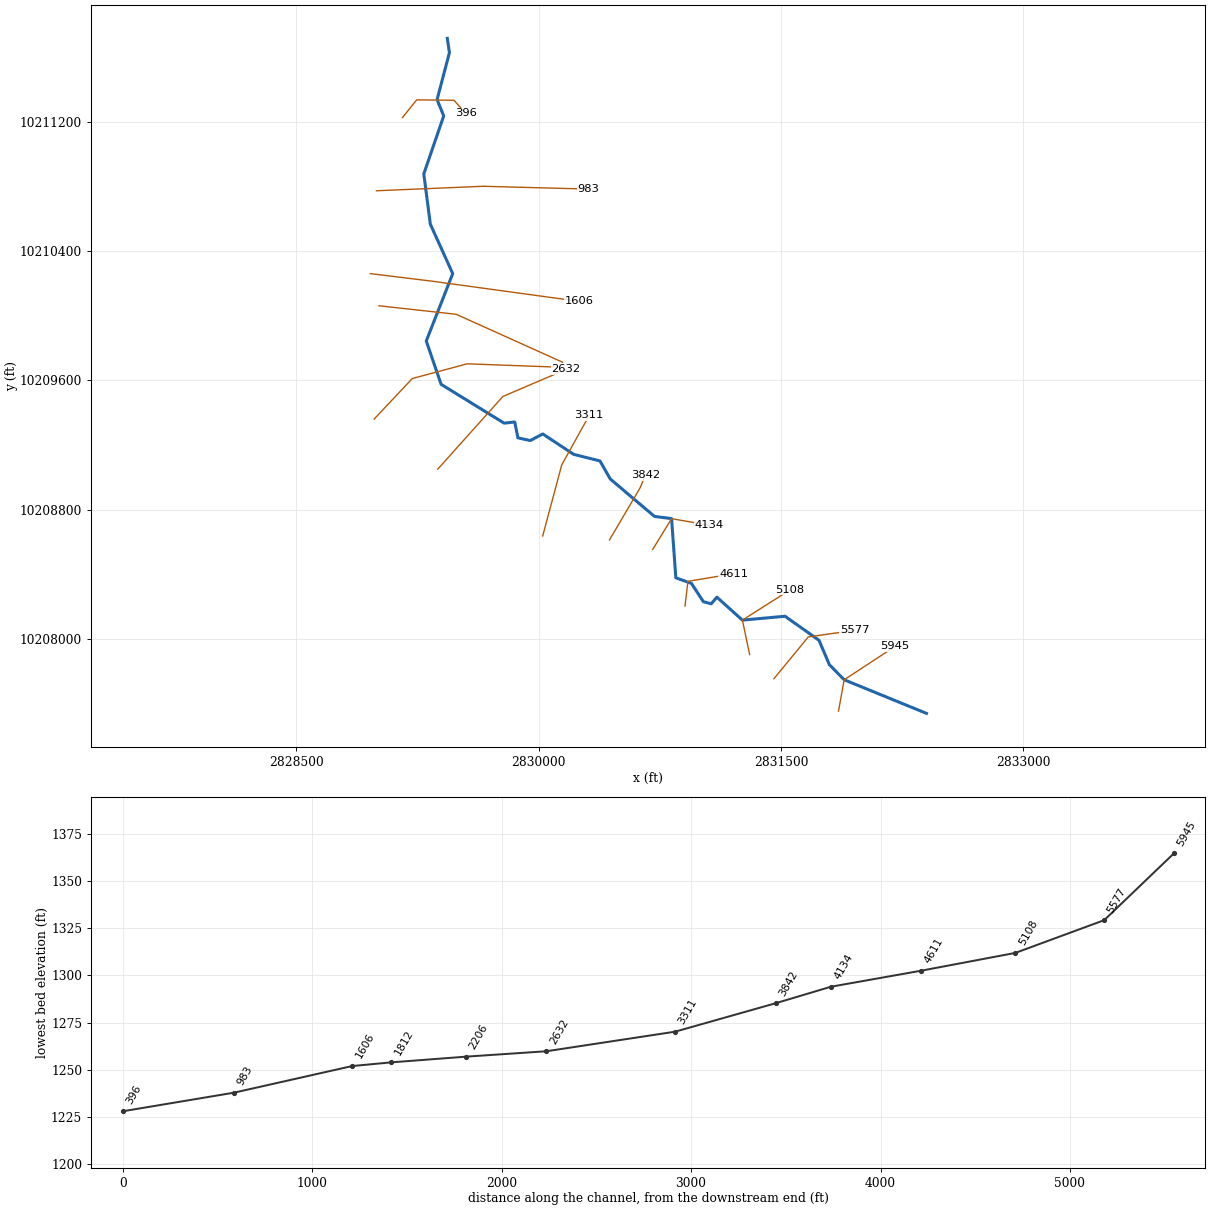
--- LITTLE LLANO 021.prj (project) ---

Proj Title=LITTLE LLANO 021 Base Level Engineering
Current Plan=p01
Default Exp/Contr=0.3,0.1
English Units
Geom File=g01
Flow File=f01
Plan File=p01
Y Axis Title=Elevation
X Axis Title(PF)=Main Channel Distance
X Axis Title(XS)=Station
BEGIN DESCRIPTION:
LITTLE LLANO 021
END DESCRIPTION:
DSS Export Rating Curves= 0
DSS Export Rating Curve Sorted= 0
DSS Export Volume Flow Curves= 0
DXF OffsetX= 0
DXF OffsetY= 0
DXF ScaleX= 1
DXF ScaleY= 10

--- LITTLE LLANO 021.p01 (plan) ---

Plan Title=Multiple Run
Short Identifier=Multiple
Geom File=g01
Flow File=f01
Subcritical Flow
K Sum by GR= 0
Std Step Tol= 0.01
Critical Tol= 0.01
Num of Std Step Trials= 20
Max Error Tol= 0.3
Flow Tol Ratio= 0.001
Split Flow NTrial= 30
Split Flow Tol= 0.02
Split Flow Ratio= 0.02
Log Output Level= 0
Friction Slope Method= 1
Unsteady Friction Slope Method= 2
Unsteady Bridges Friction Slope Method= 1
Parabolic Critical Depth
Global Vel Dist=  1 , 1 , 1
Global Log Level= 0
CheckData=True
Encroach Param= -1, 0, 0, 0
BEGIN DESCRIPTION:
Multiple Run
END DESCRIPTION:

--- LITTLE LLANO 021.f01 (steady flow) ---

Flow Title=Multiple
Number of Profiles=7
Profile Names=10-year,25-year,50-year,1pct_min,100-year,1pct_plu,500-year
River Rch & RM= LITTLE LLANO 021,Reach-1,5945
     183     283     523     416     716    1234    1060
Boundary for River Rch & Prof#=LITTLE LLANO 021,Reach-1,1
Up Type=0
Dn Type=3
Dn Slope=0.005
Boundary for River Rch & Prof#=LITTLE LLANO 021,Reach-1,2
Up Type=0
Dn Type=3
Dn Slope=0.005
Boundary for River Rch & Prof#=LITTLE LLANO 021,Reach-1,3
Up Type=0
Dn Type=3
Dn Slope=0.005
Boundary for River Rch & Prof#=LITTLE LLANO 021,Reach-1,4
Up Type=0
Dn Type=3
Dn Slope=0.005
Boundary for River Rch & Prof#=LITTLE LLANO 021,Reach-1,5
Up Type=0
Dn Type=3
Dn Slope=0.005
Boundary for River Rch & Prof#=LITTLE LLANO 021,Reach-1,6
Up Type=0
Dn Type=3
Dn Slope=0.005
Boundary for River Rch & Prof#=LITTLE LLANO 021,Reach-1,7
Up Type=0
Dn Type=3
Dn Slope=0.005

--- LITTLE LLANO 021.g01 (geometry) ---

Geom Title=Existing Conditions
Program Version=4.10

River Reach=LITTLE LLANO 021,Reach-1
Reach XY= 30
        2832400.       10207539.      2831890.75       10207747.
      2831799.25       10207840.        2831735.       10207991.
      2831524.75       10208140.        2831261.       10208116.
        2831103.       10208258.      2831068.25       10208217.
       2831019.5       10208230.      2830945.75       10208343.
        2830849.       10208378.      2830822.75       10208744.
       2830716.5       10208758.      2830442.75       10208990.
       2830379.5       10209101.       2830216.5       10209142.
       2830025.5       10209268.        2829948.       10209227.
      2829871.75       10209244.      2829852.25       10209342.
      2829786.25       10209335.      2829396.75       10209575.
      2829304.75       10209843.       2829468.5       10210260.
        2829330.       10210566.       2829289.5       10210877.
      2829412.75       10211236.      2829371.75       10211337.
      2829448.25       10211628.        2829435.       10211716.

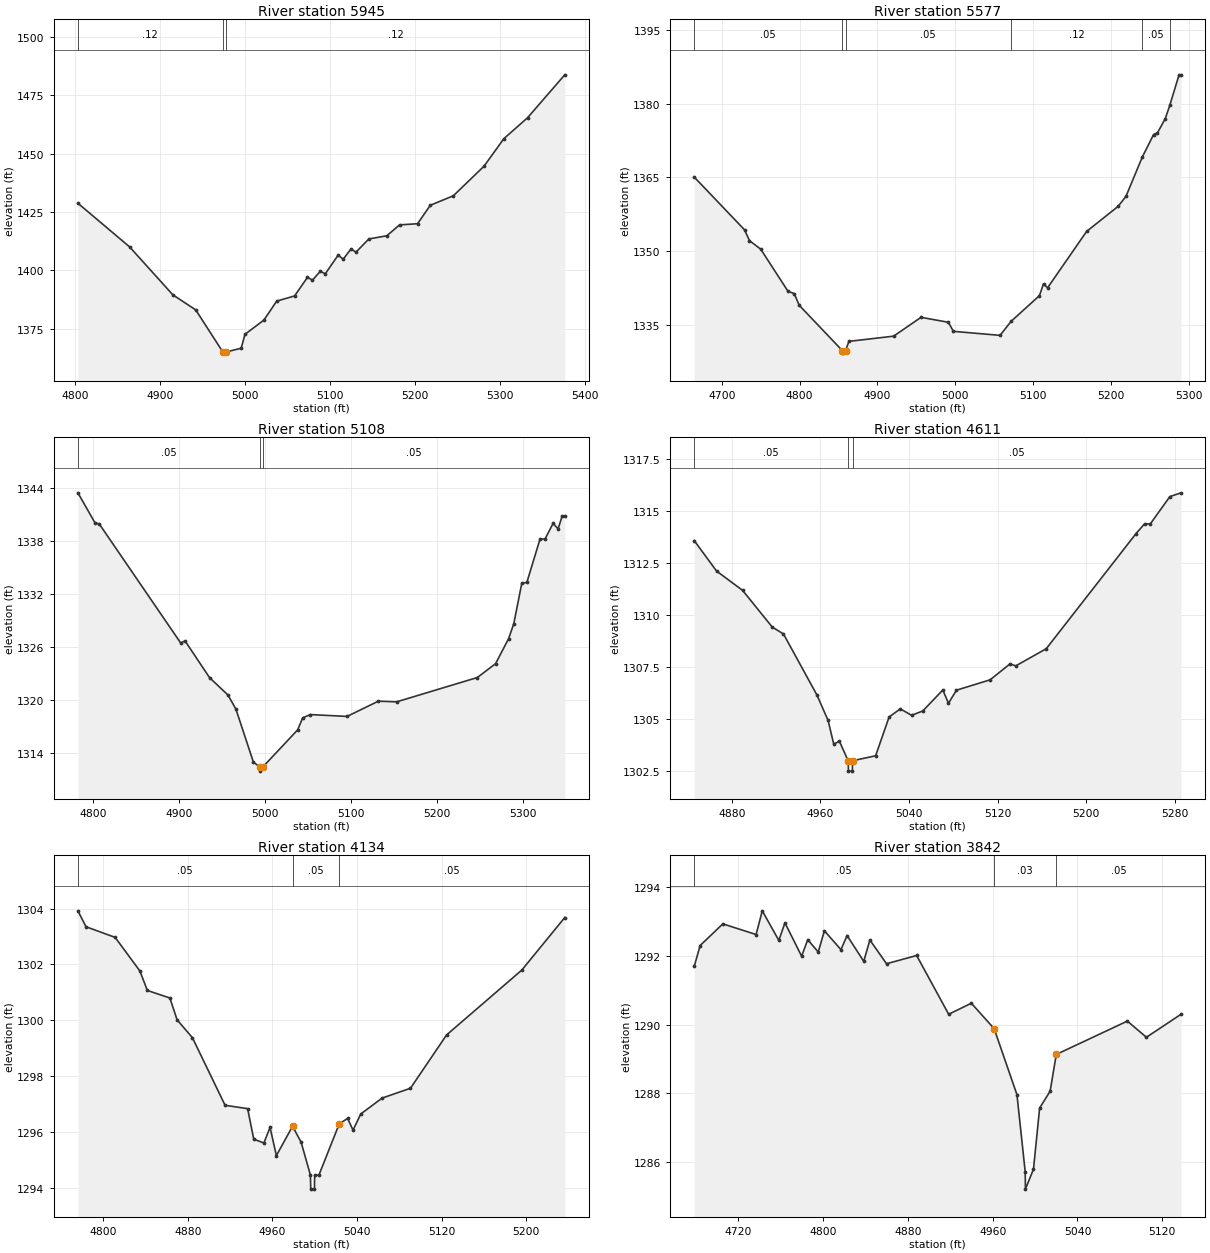
Type RM Length L Ch R = 1 ,5945    ,368,368,368
BEGIN DESCRIPTION:
LITTLE LLANO 021 11.0
END DESCRIPTION:
XS GIS Cut Line= 3
      2831855.69     10207553.14      2831890.75       10207747.
       2832205.7     10207953.12
#Sta/Elev= 30
    4803 1428.75  4863.9 1410.08  4914.8 1389.58  4941.8 1383.11  4973.7 1365.13
    4974 1364.63  4977.7 1365.13  4995.3 1366.72  4999.8 1372.67  5022.1 1378.78
  5037.2 1386.89  5058.2 1389.09  5073.4 1397.03  5079.3 1395.86  5088.5 1399.64
  5094.4 1398.58  5109.5 1406.53  5115.5 1404.83  5124.6 1409.15  5130.6 1407.85
  5145.7 1413.47  5166.8 1414.82  5181.9 1419.49    5203 1419.98  5218.1 1427.88
  5245.2 1431.94  5281.3 1444.58  5304.7 1456.37  5332.6 1465.32  5376.4 1483.67
#Mann= 3 ,-1 , 0
    4803     .12       0  4973.7     .07       0  4977.7     .12       0
Bank Sta=4973.7,4977.7
XS Rating Curve= 0 ,0
Exp/Cntr=0.3,0.1

Type RM Length L Ch R = 1 ,5577    ,469,469,469
BEGIN DESCRIPTION:
LITTLE LLANO 021 10.0
END DESCRIPTION:
XS GIS Cut Line= 3
      2831455.68      10207753.1      2831668.75       10208012.
      2831955.72     10208053.12
#Sta/Elev= 30
  4664.7 1365.05  4729.3 1354.32  4735.7 1352.12  4750.1 1350.39  4785.2 1341.81
  4793.1 1341.36  4799.6 1338.97    4855 1329.75  4855.2 1329.25    4859 1329.75
  4863.4 1331.64  4920.8  1332.7    4956 1336.53  4991.1 1335.52  4997.5 1333.68
  5057.5 1332.86  5071.6 1335.71    5108 1340.93  5113.3 1343.35  5118.4 1342.52
  5168.6 1353.99    5209 1359.08  5219.1 1361.11    5240 1369.07  5254.6 1373.69
  5259.6 1374.04  5269.7 1376.95  5275.5 1379.67  5287.3 1385.83  5289.9 1385.83
#Mann= 6 ,-1 , 0
  4664.7     .05       0    4855     .05       0    4859     .05       0
  5071.6     .12       0    5240     .05       0  5275.5     .12       0
Bank Sta=4855,4859
XS Rating Curve= 0 ,0
Exp/Cntr=0.3,0.1

Type RM Length L Ch R = 1 ,5108    ,497,497,497
BEGIN DESCRIPTION:
LITTLE LLANO 021 9.0
END DESCRIPTION:
XS GIS Cut Line= 3
      2831305.68     10207903.14        2831261.       10208116.
      2831555.71     10208303.13
#Sta/Elev= 30
  4782.5 1343.43  4802.3 1340.05  4807.4  1339.9  4902.1 1326.42  4907.2 1326.65
  4935.7 1322.49  4957.1 1320.52  4966.4 1318.92  4986.8  1312.9    4994 1312.39
  4994.2 1311.89    4998 1312.39  5038.2 1316.56  5044.1 1317.92  5052.9  1318.3
  5095.8 1318.09  5132.2 1319.82  5153.4 1319.74  5247.4  1322.5  5268.6 1324.07
  5283.8 1326.91  5289.8  1328.6  5299.1 1333.18    5305 1333.28  5320.3 1338.18
  5326.2  1338.2  5335.5 1339.96  5341.4 1339.35  5346.1  1340.8  5349.1  1340.8
#Mann= 3 ,-1 , 0
  4782.5     .05       0    4994     .03       0    4998     .05       0
Bank Sta=4994,4998
XS Rating Curve= 0 ,0
Exp/Cntr=0.3,0.1

Type RM Length L Ch R = 1 ,4611    ,477,477,477
BEGIN DESCRIPTION:
LITTLE LLANO 021 8.0
END DESCRIPTION:
XS GIS Cut Line= 3
      2830905.68     10208203.09        2830924.       10208356.
      2831205.69     10208403.11
#Sta/Elev= 30
    4846 1313.58  4866.2 1312.11  4889.7 1311.18  4916.5 1309.41  4926.6 1309.08
  4956.8 1306.14  4966.9 1304.91    4972 1303.77  4977.1 1303.91    4985 1302.97
  4985.3 1302.47  4988.8 1302.47    4989 1302.97  5009.8 1303.21    5022 1305.08
  5032.1 1305.47  5042.3 1305.16  5052.4 1305.37  5070.5 1306.38  5075.6 1305.74
  5082.8 1306.37  5113.2 1306.87  5131.2 1307.64  5136.3 1307.54  5163.9 1308.37
    5245 1313.92  5252.7 1314.39  5257.8 1314.38  5275.5  1315.7  5285.6 1315.88
#Mann= 3 ,-1 , 0
    4846     .05       0    4985     .05       0    4989     .05       0
Bank Sta=4985,4989
XS Rating Curve= 0 ,0
Exp/Cntr=0.3,0.1

Type RM Length L Ch R = 1 ,4134    ,292,292,292
BEGIN DESCRIPTION:
LITTLE LLANO 021 7.0
END DESCRIPTION:
XS GIS Cut Line= 3
       2830705.7     10208553.13      2830822.75       10208744.
      2831055.69     10208703.11
#Sta/Elev= 30
  4776.1 1303.92  4783.8 1303.35  4811.3 1302.97  4834.7 1301.77  4841.8 1301.07
  4863.1  1300.8  4869.9 1300.02  4884.4 1299.38  4915.3 1296.96  4936.6 1296.84
  4942.4 1295.75    4952 1295.61  4957.8 1296.17  4963.8 1295.16  4979.1 1296.21
  4987.2 1295.64    4996 1294.46  4996.3 1293.96  4999.8 1293.96    5000 1294.46
    5004 1294.46  5023.3  1296.3  5031.2 1296.49  5036.3 1296.07  5043.6 1296.65
  5063.9 1297.22  5090.6 1297.57  5124.8 1299.48  5195.9  1301.8  5236.5 1303.68
#Mann= 3 , 0 , 0
  4776.1     .05       0  4979.1     .05       0  5023.3     .05       0
Bank Sta=4979.1,5023.3
XS Rating Curve= 0 ,0
Exp/Cntr=0.3,0.1

Type RM Length L Ch R = 1 ,3842    ,531,531,531
BEGIN DESCRIPTION:
LITTLE LLANO 021 6.0
END DESCRIPTION:
XS GIS Cut Line= 3
      2830438.48     10208612.26      2830627.89      10208934.5
      2830661.01     10209013.24
#Sta/Elev= 30
  4678.5 1291.69  4684.1  1292.3  4705.5 1292.93  4736.9 1292.62  4742.7 1293.31
  4758.3 1292.45  4764.1 1292.96  4779.8 1291.99  4785.6 1292.47  4795.5 1292.11
  4801.3 1292.73  4816.9 1292.18  4822.7 1292.59  4838.4 1291.84  4844.2 1292.46
  4859.9 1291.77  4888.3 1292.01  4918.5  1290.3  4939.9 1290.62  4961.4 1289.88
  4982.9 1287.96  4990.7 1285.71  4990.9 1285.21  4998.5 1285.79  5004.3 1287.57
  5014.2 1288.06    5020 1289.13    5087  1290.1    5105 1289.63  5137.7  1290.3
#Mann= 3 , 0 , 0
  4678.5     .05       0  4961.4     .03       0    5020     .05       0
Bank Sta=4961.4,5020
XS Rating Curve= 0 ,0
Exp/Cntr=0.3,0.1

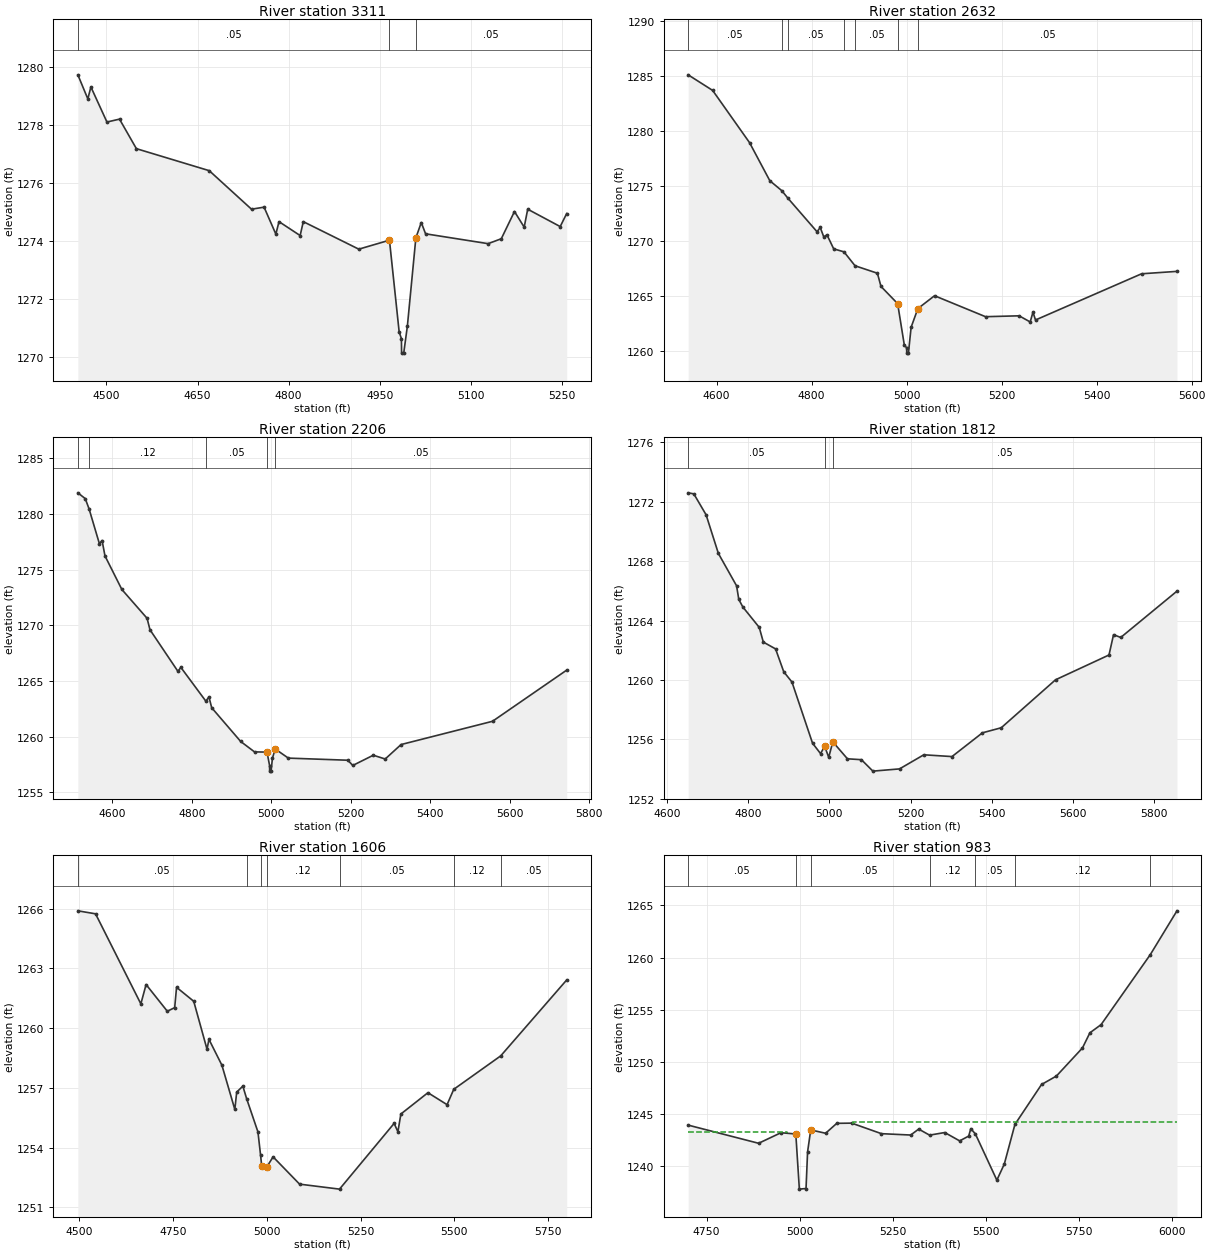
Type RM Length L Ch R = 1 ,3311    ,679,679,679
BEGIN DESCRIPTION:
LITTLE LLANO 021 5.0
END DESCRIPTION:
XS GIS Cut Line= 3
      2830025.23     10208636.85      2830143.31     10209077.17
      2830312.88     10209382.45
#Sta/Elev= 30
  4452.9 1279.74  4469.3 1278.91  4474.4 1279.32  4500.8 1278.11  4521.5 1278.21
  4549.3 1277.19  4669.3 1276.43  4738.9  1275.1  4759.6 1275.17    4779 1274.24
  4784.2 1274.67    4819 1274.19  4824.2 1274.67  4915.6 1273.72  4966.1 1274.03
  4982.1 1270.86  4985.8 1270.63  4986.1 1270.13  4989.6 1270.13  4995.6 1271.06
  5009.6 1274.11  5018.5 1274.64  5025.6 1274.25  5128.6 1273.91  5150.3 1274.08
    5172 1275.02    5188 1274.48  5193.8  1275.1  5247.3  1274.5    5258 1274.95
#Mann= 3 , 0 , 0
  4452.9     .05       0  4966.1     .05       0  5009.6     .05       0
Bank Sta=4966.1,5009.6
XS Rating Curve= 0 ,0
Exp/Cntr=0.3,0.1

Type RM Length L Ch R = 1 ,2632    ,426,426,426
BEGIN DESCRIPTION:
LITTLE LLANO 021 4.0
END DESCRIPTION:
XS GIS Cut Line= 3
      2829375.86     10209050.12      2829779.26     10209500.26
       2830169.9     10209667.05
#Sta/Elev= 30
  4539.9 1285.13  4591.5 1283.71  4669.2 1278.95  4711.9 1275.48  4737.2 1274.57
  4750.1 1273.88  4811.3 1270.83    4818 1271.22  4825.5 1270.36  4832.2 1270.55
  4846.4 1269.27    4868    1269  4891.3 1267.73  4938.4 1267.05  4945.9 1265.85
    4981 1264.28  4995.2 1260.47  4999.9 1260.27  5000.2 1259.77  5003.7 1259.77
  5009.4 1262.13  5023.6 1263.83  5058.7    1265    5166 1263.09  5236.8 1263.17
  5260.1 1262.61  5265.9  1263.5  5271.3 1262.79  5494.6    1267  5569.1 1267.22
#Mann= 7 ,-1 , 0
  4539.9     .05       0  4737.2     .12       0  4750.1     .05       0
    4868     .12       0  4891.3     .05       0    4981     .05       0
  5023.6     .05       0
Bank Sta=4981,5023.6
XS Rating Curve= 0 ,0
Exp/Cntr=0.3,0.1

Type RM Length L Ch R = 1 ,2206    ,394,394,394
BEGIN DESCRIPTION:
Mapping XS 9d4a94b4
END DESCRIPTION:
XS GIS Cut Line= 4
      2828982.26     10209360.03      2829218.42     10209610.95
      2829557.87     10209701.96       2830092.4     10209682.35
#Sta/Elev= 30
  4512.9 1281.91  4531.5 1281.39  4541.2 1280.46  4567.1 1277.34  4573.9 1277.62
  4581.2 1276.24  4623.7 1273.22  4687.2 1270.63  4694.5  1269.6  4764.9 1265.86
  4772.2 1266.22  4835.2 1263.18    4843 1263.56  4849.9 1262.59  4922.8 1259.56
  4957.7 1258.62  4989.2  1258.6  4995.7 1257.39  4995.9 1256.89  4999.4 1256.89
  5002.9 1258.06  5009.9 1258.88  5042.9 1258.06  5192.6 1257.87  5205.2  1257.4
  5256.8 1258.32  5286.8 1257.98  5326.8 1259.28    5557 1261.37  5743.8 1265.97
#Mann= 5 ,-1 , 0
  4512.9     .05       0  4541.2     .12       0  4835.2     .05       0
  4989.2     .03       0  5009.9     .05       0
Bank Sta=4989.2,5009.9
XS Rating Curve= 0 ,0
Exp/Cntr=0.3,0.1

Type RM Length L Ch R = 1 ,1812    ,206,206,206
BEGIN DESCRIPTION:
LITTLE LLANO 021 3.0
END DESCRIPTION:
XS GIS Cut Line= 3
      2829011.75      10210061.1      2829490.11     10210008.45
       2830148.2     10209711.82
#Sta/Elev= 30
  4652.5 1272.61  4666.5 1272.54  4696.7 1271.13  4726.9 1268.53  4771.7 1266.35
  4777.2 1265.43  4787.2 1264.92  4827.5 1263.55  4837.5 1262.56  4867.7  1262.1
  4887.8 1260.56    4908 1259.87  4958.7 1255.75  4978.4 1255.05  4988.5 1255.54
  4998.5  1254.8  5008.6 1255.84  5044.6  1254.7    5079 1254.64  5107.2 1253.87
  5172.8 1254.02  5232.5 1254.97  5301.9 1254.85  5376.8 1256.45  5423.1 1256.79
  5556.7 1260.02  5688.3 1261.69  5699.5 1263.06  5717.2 1262.87  5855.6 1265.99
#Mann= 3 , 0 , 0
  4652.5     .05       0  4988.5     .03       0  5008.6     .05       0
Bank Sta=4988.5,5008.6
XS Rating Curve= 0 ,0
Exp/Cntr=0.3,0.1

Type RM Length L Ch R = 1 ,1606    ,623,623,623
BEGIN DESCRIPTION:
LITTLE LLANO 021 2.0
END DESCRIPTION:
XS GIS Cut Line= 3
       2828958.8     10210260.19      2829340.33     10210213.31
      2830251.93     10210088.47
#Sta/Elev= 30
  4495.7 1265.89  4542.9 1265.74  4663.8 1261.22  4677.8 1262.19  4734.4 1260.85
  4754.1 1261.03  4759.1 1262.05  4804.9 1261.35  4840.4 1258.94  4845.5 1259.44
  4880.1 1258.14  4914.6 1255.92  4919.6 1256.79    4936 1257.09  4946.1 1256.46
  4976.3 1254.79 4983.39 1253.61  4986.4 1253.07  5000.1 1253.04  5016.7 1253.54
  5087.4 1252.17    5194 1251.92  5339.7 1255.22  5349.8  1254.8  5357.7 1255.69
  5429.9 1256.76    5481 1256.16  5498.8 1256.93  5624.2 1258.61  5800.2 1262.42
#Mann= 7 ,-1 , 0
  4495.7     .05       0  4946.1     .12       0 4983.39     .03       0
  5000.1     .12       0    5194     .05       0  5498.8     .12       0
  5624.2     .05       0
Bank Sta=4986.4,5000.1
XS Rating Curve= 0 ,0
Exp/Cntr=0.3,0.1

Type RM Length L Ch R = 1 ,983     ,587,587,587
BEGIN DESCRIPTION:
Mapping XS a4cff859
END DESCRIPTION:
XS GIS Cut Line= 3
       2828996.5      10210772.8      2829656.32     10210800.58
      2830309.58     10210783.22
#Sta/Elev= 30
  4700.4 1243.95  4889.8 1242.21  4949.8 1243.22  4989.8  1243.1 4999.34 1237.82
 5017.29 1237.88 5021.46 1241.39  5029.9 1243.49  5069.9 1243.17  5099.9 1244.12
    5140 1244.14    5220 1243.13  5298.6    1243  5320.1 1243.57  5349.3 1242.99
  5390.2 1243.24  5430.2 1242.44  5454.5  1242.9  5460.2 1243.61  5472.6  1243.1
  5530.2 1238.68  5550.2 1240.22  5578.8 1244.02  5650.3 1247.84  5690.3 1248.65
  5760.3 1251.34  5780.3 1252.79  5810.3 1253.57  5942.7 1260.28  6014.3 1264.47
#Mann= 7 ,-1 , 0
  4700.4     .05       0  4989.8     .03       0  5029.9     .05       0
  5349.3     .12       0  5472.6     .05       0  5578.8     .12       0
  5942.7     .05       0
#XS Ineff= 2 , 0
         4967.35  1243.3 5142.86         1244.25
Permanent Ineff=
       F       F
Bank Sta=4989.8,5029.9
XS Rating Curve= 0 ,0
Exp/Cntr=0.3,0.1

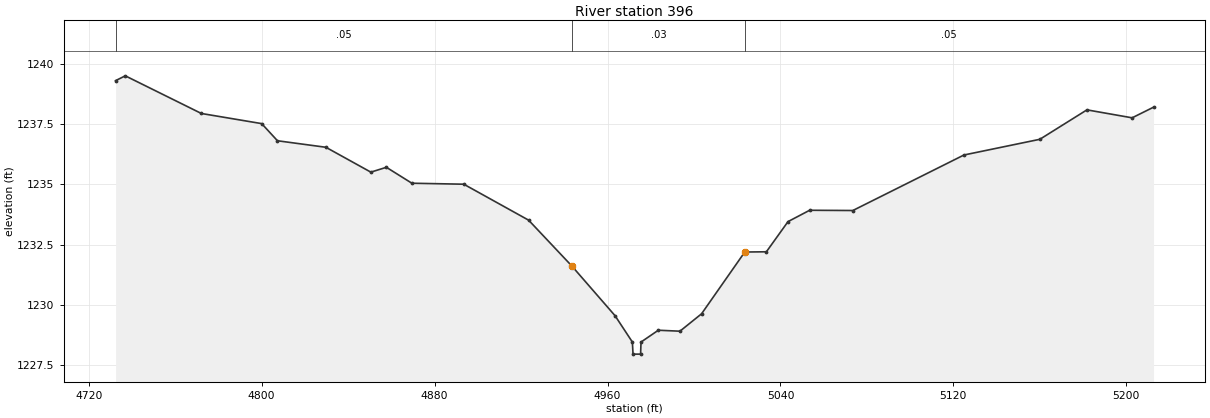
Type RM Length L Ch R = 1 ,396     ,0,0,0
BEGIN DESCRIPTION:
LITTLE LLANO 021 1.0
END DESCRIPTION:
XS GIS Cut Line= 4
      2829157.29     10211225.39      2829245.48     10211335.28
       2829476.7     10211332.82      2829548.04     10211251.64
#Sta/Elev= 30
  4732.4  1239.3  4736.9  1239.5  4772.1 1237.94    4800 1237.52  4807.3 1236.81
  4829.7 1236.54  4850.5 1235.51  4857.7 1235.71  4869.5 1235.05  4893.5 1235.01
  4923.5 1233.52  4943.5 1231.62  4963.5 1229.56  4971.5 1228.47  4971.8 1227.97
  4975.3 1227.97  4975.5 1228.47  4983.5 1228.96  4993.5 1228.92  5003.5 1229.64
  5023.5  1232.2  5033.5 1232.21  5043.5 1233.46  5053.5 1233.93  5073.5 1233.92
  5124.9 1236.22    5160 1236.87  5181.8 1238.09  5202.7 1237.76  5212.6  1238.2
#Mann= 3 , 0 , 0
  4732.4     .05       0  4943.5     .03       0  5023.5     .05       0
Bank Sta=4943.5,5023.5
XS Rating Curve= 0 ,0
Exp/Cntr=0.3,0.1

Chan Stop Cuts=-1
Use User Specified Reach Order=0
Composite Channel Slope=5