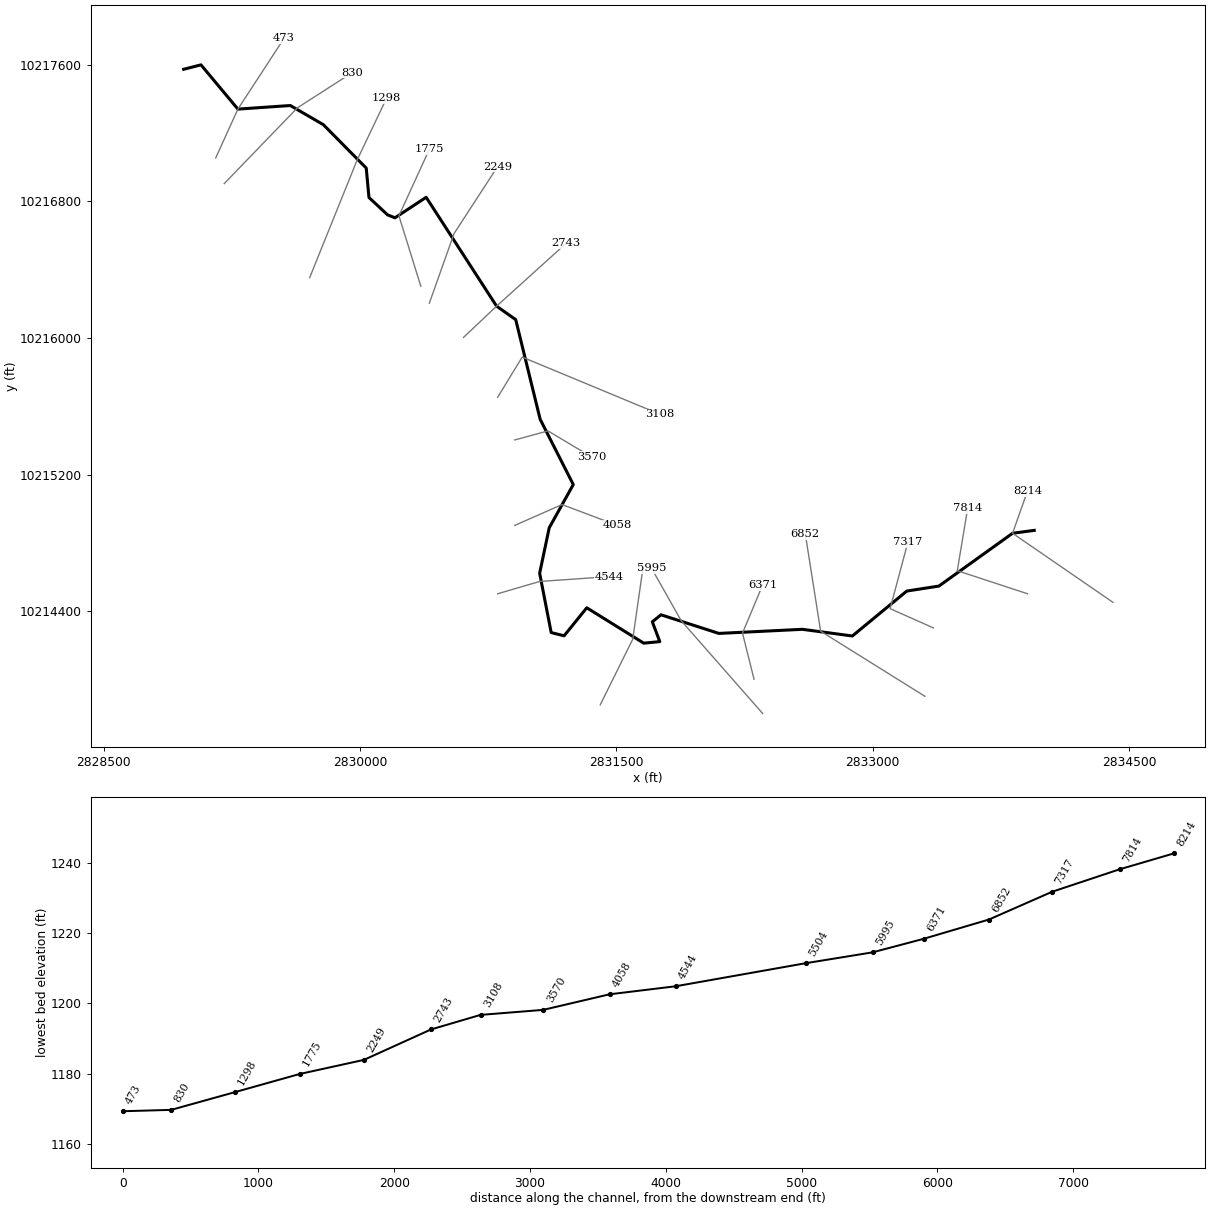
--- LITTLE LLANO 022.prj (project) ---

Proj Title=LITTLE LLANO 022 Base Level Engineering
Current Plan=p01
Default Exp/Contr=0.3,0.1
English Units
Geom File=g01
Flow File=f01
Plan File=p01
BEGIN DESCRIPTION:
LITTLE LLANO 022
END DESCRIPTION:

--- LITTLE LLANO 022.p01 (plan) ---

Plan Title=Multiple Run
Short Identifier=Multiple
Geom File=g01
Flow File=f01
Subcritical Flow
K Sum by GR= 0
Std Step Tol= 0.01
Critical Tol= 0.01
Num of Std Step Trials= 20
Max Error Tol= 0.3
Flow Tol Ratio= 0.001
Split Flow NTrial= 30
Split Flow Tol= 0.02
Split Flow Ratio= 0.02
Log Output Level= 0
Friction Slope Method= 1
Unsteady Friction Slope Method= 2
Unsteady Bridges Friction Slope Method= 1
Parabolic Critical Depth
Global Vel Dist=  1 , 1 , 1
Global Log Level= 0
CheckData=True
Encroach Param= -1, 0, 0, 0
BEGIN DESCRIPTION:
Multiple Run
END DESCRIPTION:

--- LITTLE LLANO 022.f01 (steady flow) ---

Flow Title=Multiple
Number of Profiles=7
Profile Names=10-year,25-year,50-year,1pct_min,100-year,1pct_plu,500-year
River Rch & RM= LITTLE LLANO 022,Reach-1,8214
     208     324     814     687    1158    1952    1771
River Rch & RM= LITTLE LLANO 022,Reach-1,6371
     313     497    1350    1164    1948    3261    2957
River Rch & RM= LITTLE LLANO 022,Reach-1,5504
     685    1142    2472    1921    3540    6523    5149
Boundary for River Rch & Prof#=LITTLE LLANO 022,Reach-1,1
Up Type=0
Dn Type=3
Dn Slope=0.005
Boundary for River Rch & Prof#=LITTLE LLANO 022,Reach-1,2
Up Type=0
Dn Type=3
Dn Slope=0.005
Boundary for River Rch & Prof#=LITTLE LLANO 022,Reach-1,3
Up Type=0
Dn Type=3
Dn Slope=0.005
Boundary for River Rch & Prof#=LITTLE LLANO 022,Reach-1,4
Up Type=0
Dn Type=3
Dn Slope=0.005
Boundary for River Rch & Prof#=LITTLE LLANO 022,Reach-1,5
Up Type=0
Dn Type=3
Dn Slope=0.005
Boundary for River Rch & Prof#=LITTLE LLANO 022,Reach-1,6
Up Type=0
Dn Type=3
Dn Slope=0.005
Boundary for River Rch & Prof#=LITTLE LLANO 022,Reach-1,7
Up Type=0
Dn Type=3
Dn Slope=0.005

--- LITTLE LLANO 022.g01 (geometry) ---

Geom Title=Existing Conditions

River Reach=LITTLE LLANO 022,Reach-1
Reach XY= 30
      2833945.50     10214874.00      2833818.50     10214857.00
      2833387.50     10214548.00      2833199.75     10214519.00
      2832881.25     10214256.00      2832588.50     10214295.00
      2832100.00     10214271.00      2831761.25     10214380.00
      2831710.50     10214339.00      2831754.25     10214223.00
      2831660.25     10214214.00      2831327.00     10214421.00
      2831194.25     10214257.00      2831118.75     10214276.00
      2831051.25     10214623.00      2831107.25     10214889.00
      2831248.00     10215142.00      2831054.25     10215524.00
      2830911.25     10216107.00      2830799.25     10216186.00
      2830387.25     10216823.00      2830204.75     10216703.00
      2830161.50     10216720.00      2830052.50     10216822.00
      2830036.50     10216994.00      2829785.50     10217248.00
      2829592.25     10217360.00      2829285.50     10217339.00
      2829069.50     10217598.00      2828968.25     10217572.00

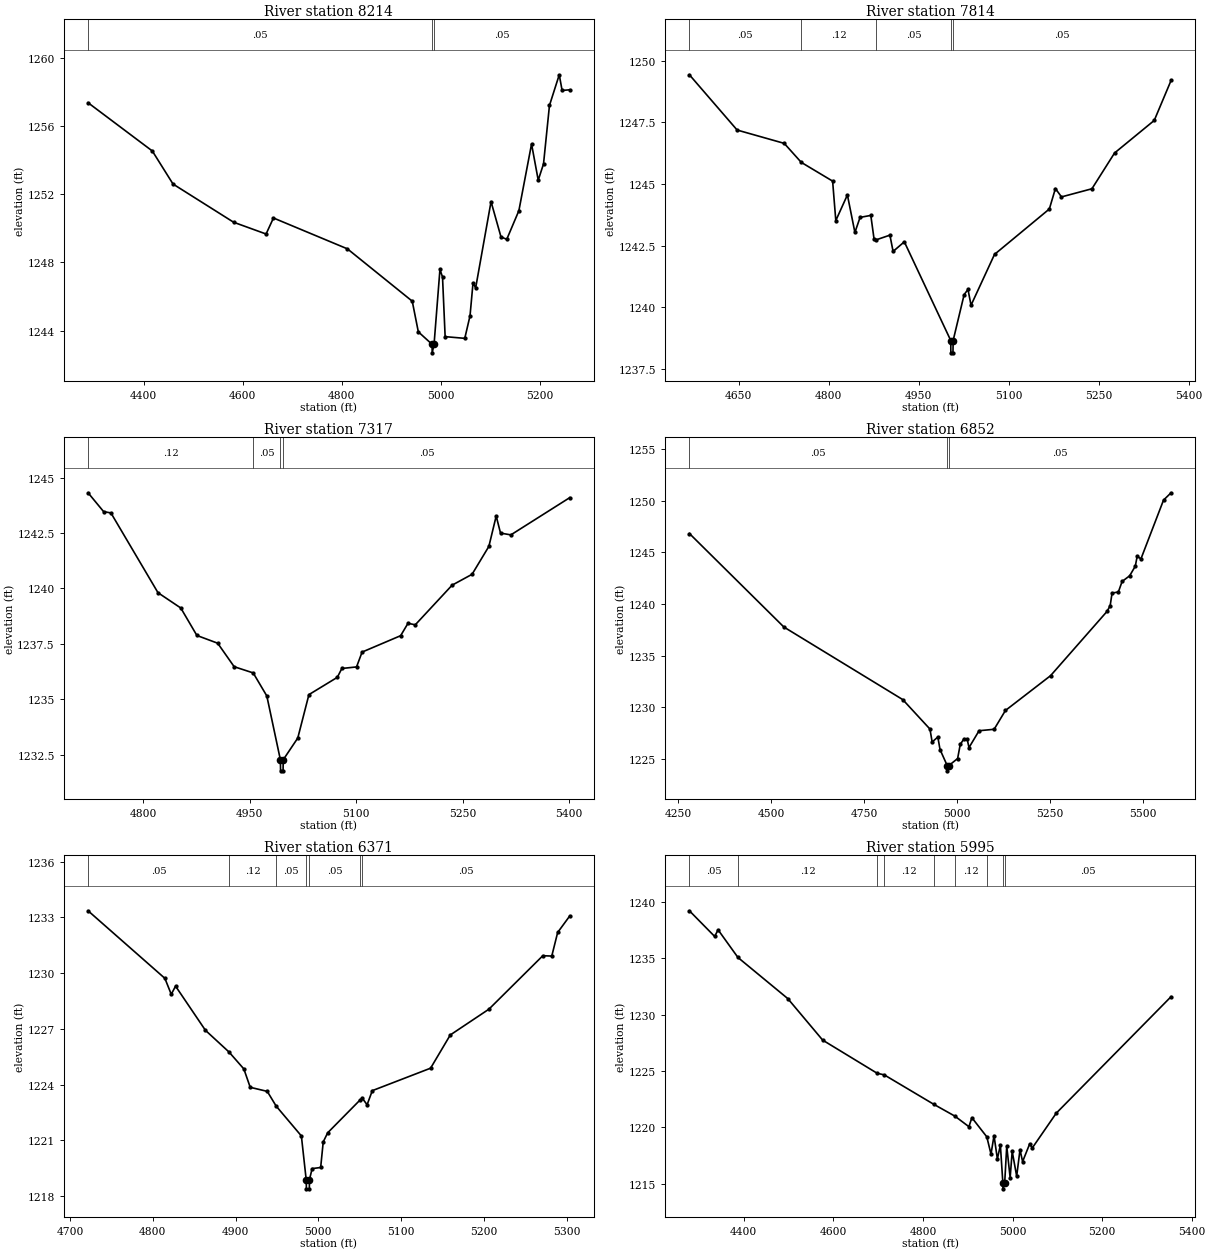
Type RM Length L Ch R = 1,8214,400,400,400
BEGIN DESCRIPTION:
LITTLE LLANO 022 17.0
END DESCRIPTION:
XS GIS Cut Line= 3
      2834405.70     10214453.10      2833818.50     10214857.00
      2833905.68     10215103.11
#Sta/Elev= 30
  4287.3 1257.36  4417.2 1254.53  4459.1 1252.59  4581.6 1250.35  4647.2 1249.66
  4662.1 1250.60  4811.6 1248.79  4942.7 1245.72  4955.0 1243.92  4982.8 1243.19
  4983.0 1242.69  4986.8 1243.19  4998.7 1247.58  5003.9 1247.14  5009.2 1243.64
  5048.9 1243.54  5059.5 1244.86  5065.6 1246.80  5070.9 1246.50  5102.0 1251.56
  5122.1 1249.49  5133.8 1249.35  5158.3 1251.03  5183.9 1254.94  5197.4 1252.82
  5208.1 1253.77  5220.1 1257.20  5239.9 1259.00  5245.7 1258.08  5261.1 1258.12
#Mann=3,-1,0
  4287.3    0.05       0  4982.8    0.05       0  4986.8    0.05       0
Bank Sta=4982.8,4986.8
Exp/Cntr=0.3,0.1

Type RM Length L Ch R = 1,7814,497,497,497
BEGIN DESCRIPTION:
LITTLE LLANO 022 16.0
END DESCRIPTION:
XS GIS Cut Line= 3
      2833905.65     10214503.12      2833495.25     10214638.00
      2833555.69     10215003.13
#Sta/Elev= 30
  4568.0 1249.43  4647.5 1247.19  4725.9 1246.65  4754.3 1245.88  4806.5 1245.12
  4811.8 1243.52  4831.1 1244.56  4843.6 1243.04  4852.2 1243.65  4870.1 1243.73
  4875.4 1242.79  4879.0 1242.74  4901.9 1242.93  4907.2 1242.27  4925.9 1242.66
  5003.2 1238.66  5003.4 1238.16  5006.9 1238.16  5007.2 1238.66  5025.5 1240.52
  5031.9 1240.73  5037.0 1240.09  5076.1 1242.15  5167.4 1243.99  5177.5 1244.82
  5187.6 1244.48  5238.3 1244.81  5276.0 1246.26  5342.1 1247.58  5370.1 1249.20
#Mann=5,-1,0
  4568.0    0.05       0  4754.3    0.12       0  4879.0    0.05       0
  5003.2    0.05       0  5007.2    0.05       0
Bank Sta=5003.2,5007.2
Exp/Cntr=0.3,0.1

Type RM Length L Ch R = 1,7317,465,465,465
BEGIN DESCRIPTION:
LITTLE LLANO 022 15.0
END DESCRIPTION:
XS GIS Cut Line= 3
      2833355.71     10214303.10      2833102.00     10214416.00
      2833205.70     10214803.15
#Sta/Elev= 30
  4722.3 1244.32  4744.2 1243.47  4754.5 1243.41  4820.8 1239.81  4852.9 1239.12
  4875.6 1237.88  4904.9 1237.53  4928.1 1236.47  4954.9 1236.19  4974.1 1235.15
  4993.2 1232.27  4993.5 1231.77  4997.0 1231.77  4997.2 1232.27  5017.7 1233.25
  5033.4 1235.21  5073.4 1235.99  5079.8 1236.39  5100.5 1236.46  5108.3 1237.13
  5162.6 1237.87  5173.0 1238.43  5183.2 1238.36  5235.1 1240.15  5263.2 1240.64
  5286.9 1241.90  5297.2 1243.27  5303.3 1242.50  5317.9 1242.42  5400.8 1244.10
#Mann=4,-1,0
  4722.3    0.12       0  4954.9    0.05       0  4993.2    0.05       0
  4997.2    0.05       0
Bank Sta=4993.2,4997.2
Exp/Cntr=0.3,0.1

Type RM Length L Ch R = 1,6852,481,481,481
BEGIN DESCRIPTION:
LITTLE LLANO 022 14.0
END DESCRIPTION:
XS GIS Cut Line= 3
      2833305.68     10213903.11      2832695.50     10214284.00
      2832605.68     10214853.16
#Sta/Elev= 30
  4280.7 1246.83  4534.9 1237.78  4854.6 1230.76  4927.7 1227.91  4933.6 1226.66
  4948.9 1227.14  4954.8 1225.93  4974.2 1224.37  4974.5 1223.87  4978.2 1224.37
  5002.1 1225.06  5009.2 1226.43  5019.3 1226.97  5027.7 1226.95  5032.7 1226.12
  5059.8 1227.75  5100.3 1227.89  5130.7 1229.71  5252.2 1233.08  5404.1 1239.30
  5412.4 1239.85  5417.5 1241.07  5434.4 1241.17  5444.5 1242.19  5464.8 1242.74
  5480.0 1243.67  5485.0 1244.62  5495.2 1244.38  5555.9 1250.06  5576.2 1250.77
#Mann=3,-1,0
  4280.7    0.05       0  4974.2    0.05       0  4978.2    0.05       0
Bank Sta=4974.2,4978.2
Exp/Cntr=0.3,0.1

Type RM Length L Ch R = 1,6371,376,376,376
BEGIN DESCRIPTION:
LITTLE LLANO 022 13.0
END DESCRIPTION:
XS GIS Cut Line= 3
      2832305.69     10214003.10      2832238.25     10214273.00
      2832355.67     10214553.08
#Sta/Elev= 30
  4721.8 1233.36  4814.6 1229.72  4822.3 1228.86  4827.5 1229.30  4863.6 1226.92
  4892.1 1225.75  4910.0 1224.84  4917.7 1223.85  4938.3 1223.63  4949.0 1222.84
  4979.5 1221.23  4985.3 1218.88  4985.6 1218.38  4989.1 1218.38  4989.3 1218.88
  4992.5 1219.47  5002.8 1219.53  5005.9 1220.91  5011.3 1221.40  5050.7 1223.18
  5053.3 1223.25  5058.9 1222.91  5065.2 1223.67  5135.6 1224.88  5159.4 1226.67
  5206.1 1228.06  5271.2 1230.94  5282.0 1230.92  5289.1 1232.19  5303.7 1233.08
#Mann=7,-1,0
  4721.8    0.05       0  4892.1    0.12       0  4949.0    0.05       0
  4985.3    0.05       0  4989.3    0.05       0  5050.7    0.12       0
  5053.3    0.05       0
Bank Sta=4985.3,4989.3
Exp/Cntr=0.3,0.1

Type RM Length L Ch R = 1,5995,491,491,491
BEGIN DESCRIPTION:
LITTLE LLANO 022 12.0
END DESCRIPTION:
XS GIS Cut Line= 3
      2832355.67     10213803.13      2831879.75     10214345.00
      2831705.67     10214653.13
#Sta/Elev= 30
  4278.8 1239.23  4335.2 1236.95  4342.8 1237.54  4387.2 1235.08  4498.4 1231.43
  4576.3 1227.74  4697.7 1224.80  4713.9 1224.65  4823.8 1222.05  4871.3 1220.99
  4902.7 1220.05  4909.3 1220.85  4942.6 1219.15  4952.0 1217.61  4958.7 1219.26
  4966.2 1217.19  4972.9 1218.41  4978.5 1215.03  4978.7 1214.53  4982.5 1215.03
  4987.1 1218.32  4994.7 1215.52  4999.3 1217.86  5009.3 1215.65  5016.7 1218.01
  5022.5 1216.95  5038.4 1218.53  5044.1 1218.16  5097.6 1221.25  5353.9 1231.60
#Mann=9,-1,0
  4278.8    0.05       0  4387.2    0.12       0  4697.7    0.05       0
  4713.9    0.12       0  4823.8    0.05       0  4871.3    0.12       0
  4942.6    0.05       0  4978.5    0.05       0  4982.5    0.05       0
Bank Sta=4978.5,4982.5
Exp/Cntr=0.3,0.1

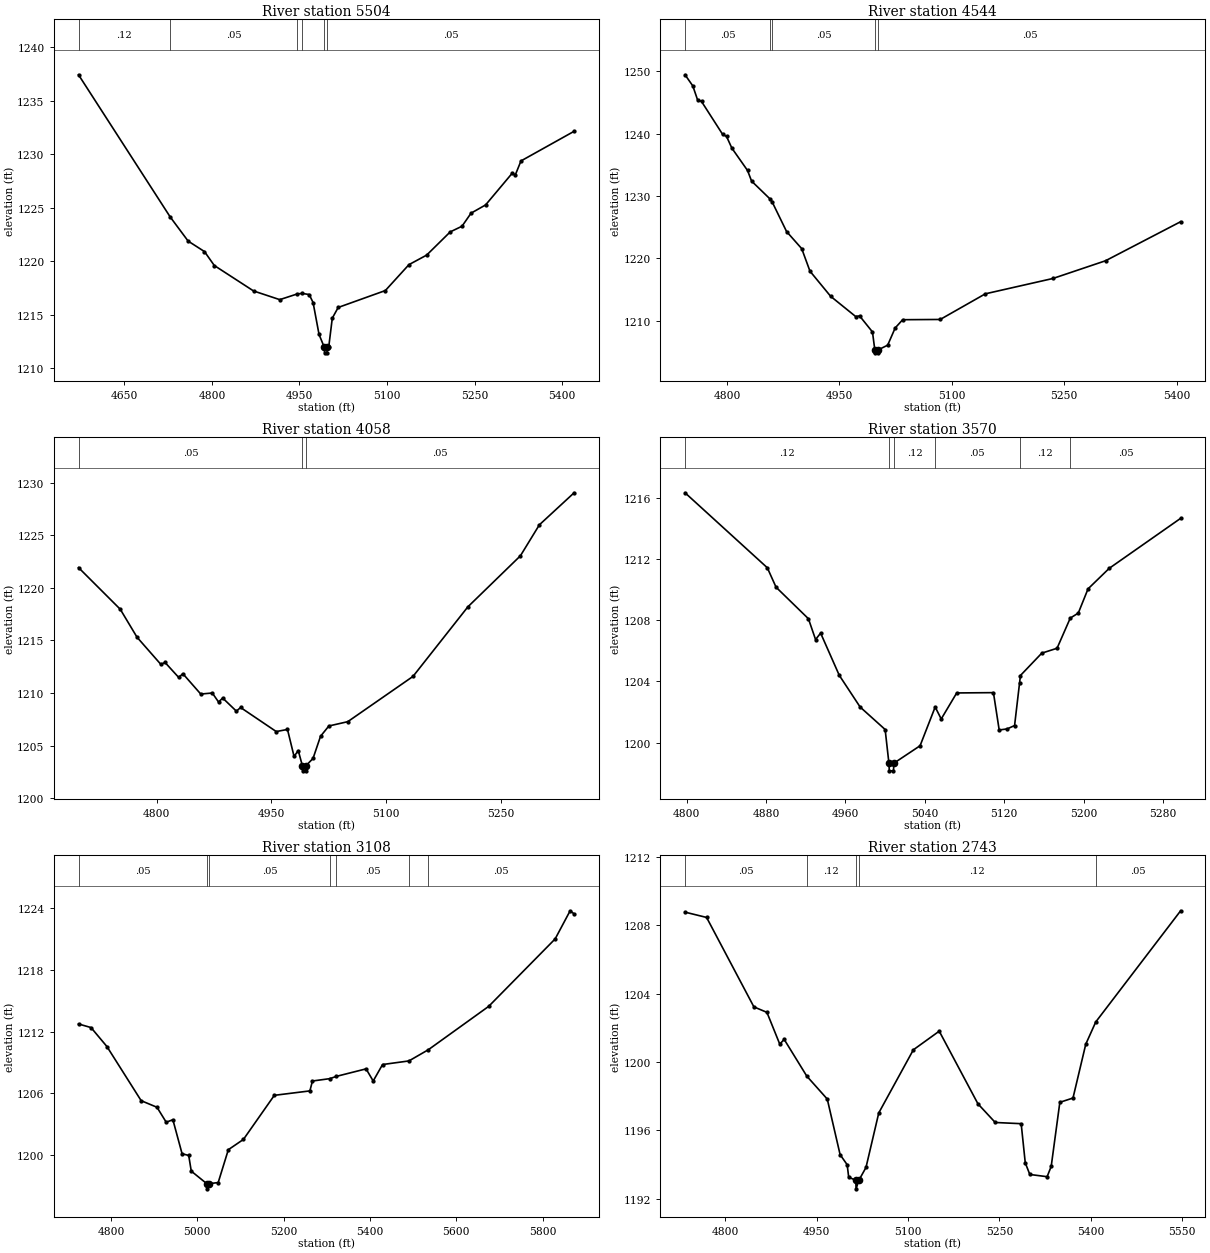
Type RM Length L Ch R = 1,5504,960,960,960
BEGIN DESCRIPTION:
LITTLE LLANO 022 11.0
END DESCRIPTION:
XS GIS Cut Line= 3
      2831405.67     10213853.09      2831596.00     10214237.00
      2831655.69     10214653.14
#Sta/Elev= 30
  4571.5 1237.43  4728.5 1224.15  4759.3 1221.89  4787.3 1220.91  4804.1 1219.61
  4871.4 1217.23  4916.2 1216.42  4946.6 1216.96  4954.8 1217.00  4966.6 1216.90
  4973.3 1216.15  4983.5 1213.17  4992.6 1211.95  4993.0 1211.45  4997.1 1211.45
  4997.4 1211.95  5000.0 1211.95  5006.2 1214.69  5016.3 1215.69  5097.1 1217.27
  5137.5 1219.69  5167.8 1220.58  5208.2 1222.75  5228.4 1223.28  5243.9 1224.50
  5268.8 1225.27  5314.5 1228.24  5319.6 1228.06  5329.4 1229.38  5420.4 1232.15
#Mann=6,-1,0
  4571.5    0.12       0  4728.5    0.05       0  4946.6    0.12       0
  4954.8    0.05       0  4992.6    0.05       0  4997.4    0.05       0
Bank Sta=4992.6,4997.4
Exp/Cntr=0.3,0.1

Type RM Length L Ch R = 1,4544,486,486,486
BEGIN DESCRIPTION:
LITTLE LLANO 022 10.0
END DESCRIPTION:
XS GIS Cut Line= 3
      2830805.66     10214503.10      2831051.25     10214575.00
      2831455.67     10214603.11
#Sta/Elev= 30
  4744.1 1249.44  4754.5 1247.65  4760.8 1245.42  4766.1 1245.16  4794.3 1239.88
  4799.5 1239.55  4806.6 1237.68  4827.5 1234.10  4832.9 1232.40  4857.2 1229.57
  4860.1 1229.12  4879.6 1224.31  4899.8 1221.57  4910.8 1217.96  4938.4 1213.93
  4971.8 1210.69  4977.0 1210.79  4994.2 1208.22  4997.3 1205.37  4997.6 1204.87
  5001.8 1204.87  5002.2 1205.37  5014.5 1206.10  5024.5 1208.86  5034.5 1210.18
  5084.6 1210.22  5144.8 1214.33  5235.0 1216.79  5305.2 1219.63  5405.4 1225.89
#Mann=5,-1,0
  4744.1    0.05       0  4857.2    0.12       0  4860.1    0.05       0
  4997.3    0.03       0  5002.2    0.05       0
Bank Sta=4997.3,5002.2
Exp/Cntr=0.3,0.1

Type RM Length L Ch R = 1,4058,488,488,488
BEGIN DESCRIPTION:
LITTLE LLANO 022 9.0
END DESCRIPTION:
XS GIS Cut Line= 3
      2830905.69     10214903.11      2831182.00     10215025.00
      2831505.71     10214903.10
#Sta/Elev= 30
  4698.0 1221.94  4752.6 1217.97  4774.5 1215.31  4805.7 1212.72  4811.1 1212.91
  4829.0 1211.48  4834.4 1211.84  4857.8 1209.90  4872.9 1210.00  4881.1 1209.14
  4886.5 1209.52  4904.4 1208.27  4909.9 1208.62  4956.5 1206.33  4971.2 1206.53
  4979.8 1203.96  4985.3 1204.52  4990.6 1203.09  4991.0 1202.59  4995.2 1202.59
  4995.5 1203.09  5004.6 1203.77  5014.4 1205.88  5025.3 1206.86  5050.0 1207.27
  5135.3 1211.58  5207.0 1218.20  5275.7 1223.06  5300.5 1226.01  5345.9 1229.06
#Mann=3,-1,0
  4698.0    0.05       0  4990.6    0.03       0  4995.5    0.05       0
Bank Sta=4990.6,4995.5
Exp/Cntr=0.3,0.1

Type RM Length L Ch R = 1,3570,462,462,462
BEGIN DESCRIPTION:
LITTLE LLANO 022 8.0
END DESCRIPTION:
XS GIS Cut Line= 3
      2830905.71     10215403.12      2831100.25     10215456.00
      2831355.69     10215303.11
#Sta/Elev= 30
  4798.4 1216.33  4881.3 1211.43  4890.1 1210.16  4922.7 1208.10  4929.9 1206.74
  4935.0 1207.16  4953.8 1204.40  4974.8 1202.33  5000.0 1200.86  5003.8 1198.66
  5004.2 1198.16  5008.4 1198.16  5008.8 1198.66  5035.2 1199.80  5050.4 1202.33
  5056.5 1201.55  5072.1 1203.25  5109.1 1203.27  5114.9 1200.83  5122.9 1200.90
  5130.4 1201.12  5135.4 1203.89  5136.3 1204.39  5157.8 1205.85  5173.2 1206.17
  5186.5 1208.14  5194.6 1208.47  5204.4 1210.05  5225.7 1211.39  5297.7 1214.66
#Mann=6,-1,0
  4798.4    0.12       0  5003.8    0.07       0  5008.8    0.12       0
  5050.4    0.05       0  5135.4    0.12       0  5186.5    0.05       0
Bank Sta=5003.8,5008.8
Exp/Cntr=0.3,0.1

Type RM Length L Ch R = 1,3108,365,365,365
BEGIN DESCRIPTION:
LITTLE LLANO 022 7.0
END DESCRIPTION:
XS GIS Cut Line= 3
      2830805.68     10215653.10      2830949.25     10215888.00
      2831755.68     10215553.11
#Sta/Elev= 30
  4724.7 1212.74  4753.7 1212.39  4790.5 1210.55  4869.9 1205.29  4906.6 1204.65
  4927.9 1203.20  4943.4 1203.44  4964.7 1200.14  4980.1 1199.97  4986.0 1198.45
  5022.0 1197.23  5022.4 1196.73  5027.0 1197.23  5048.4 1197.34  5071.9 1200.53
  5106.9 1201.53  5178.5 1205.81  5260.9 1206.24  5266.8 1207.20  5307.1 1207.43
  5322.2 1207.65  5391.1 1208.38  5407.6 1207.20  5429.3 1208.80  5490.4 1209.15
  5535.5 1210.24  5675.3 1214.45  5829.3 1221.00  5864.0 1223.73  5873.2 1223.43
#Mann=7,-1,0
  4724.7    0.05       0  5022.0    0.05       0  5027.0    0.05       0
  5307.1    0.12       0  5322.2    0.05       0  5490.4    0.12       0
  5535.5    0.05       0
Bank Sta=5022,5027
Exp/Cntr=0.3,0.1

Type RM Length L Ch R = 1,2743,494,494,494
BEGIN DESCRIPTION:
LITTLE LLANO 022 6.0
END DESCRIPTION:
XS GIS Cut Line= 3
      2830605.68     10216003.11      2830799.25     10216186.00
      2831205.69     10216553.12
#Sta/Elev= 30
  4733.7 1208.76  4769.1 1208.45  4846.8 1203.22  4868.2 1202.90  4889.3 1201.04
  4896.5 1201.32  4933.7 1199.17  4967.3 1197.83  4988.4 1194.58  5000.0 1193.99
  5002.5 1193.26  5014.2 1193.08  5014.6 1192.58  5019.2 1193.08  5030.9 1193.83
  5051.9 1197.02  5108.7 1200.71  5151.2 1201.80  5214.8 1197.55  5243.2 1196.46
  5285.8 1196.39  5292.5 1194.10  5300.0 1193.42  5328.4 1193.29  5335.1 1193.89
  5349.3 1197.64  5370.9 1197.89  5391.9 1201.04  5408.3 1202.34  5547.7 1208.84
#Mann=5,-1,0
  4733.7    0.05       0  4933.7    0.12       0  5014.2    0.07       0
  5019.2    0.12       0  5408.3    0.05       0
Bank Sta=5014.2,5019.2
Exp/Cntr=0.3,0.1

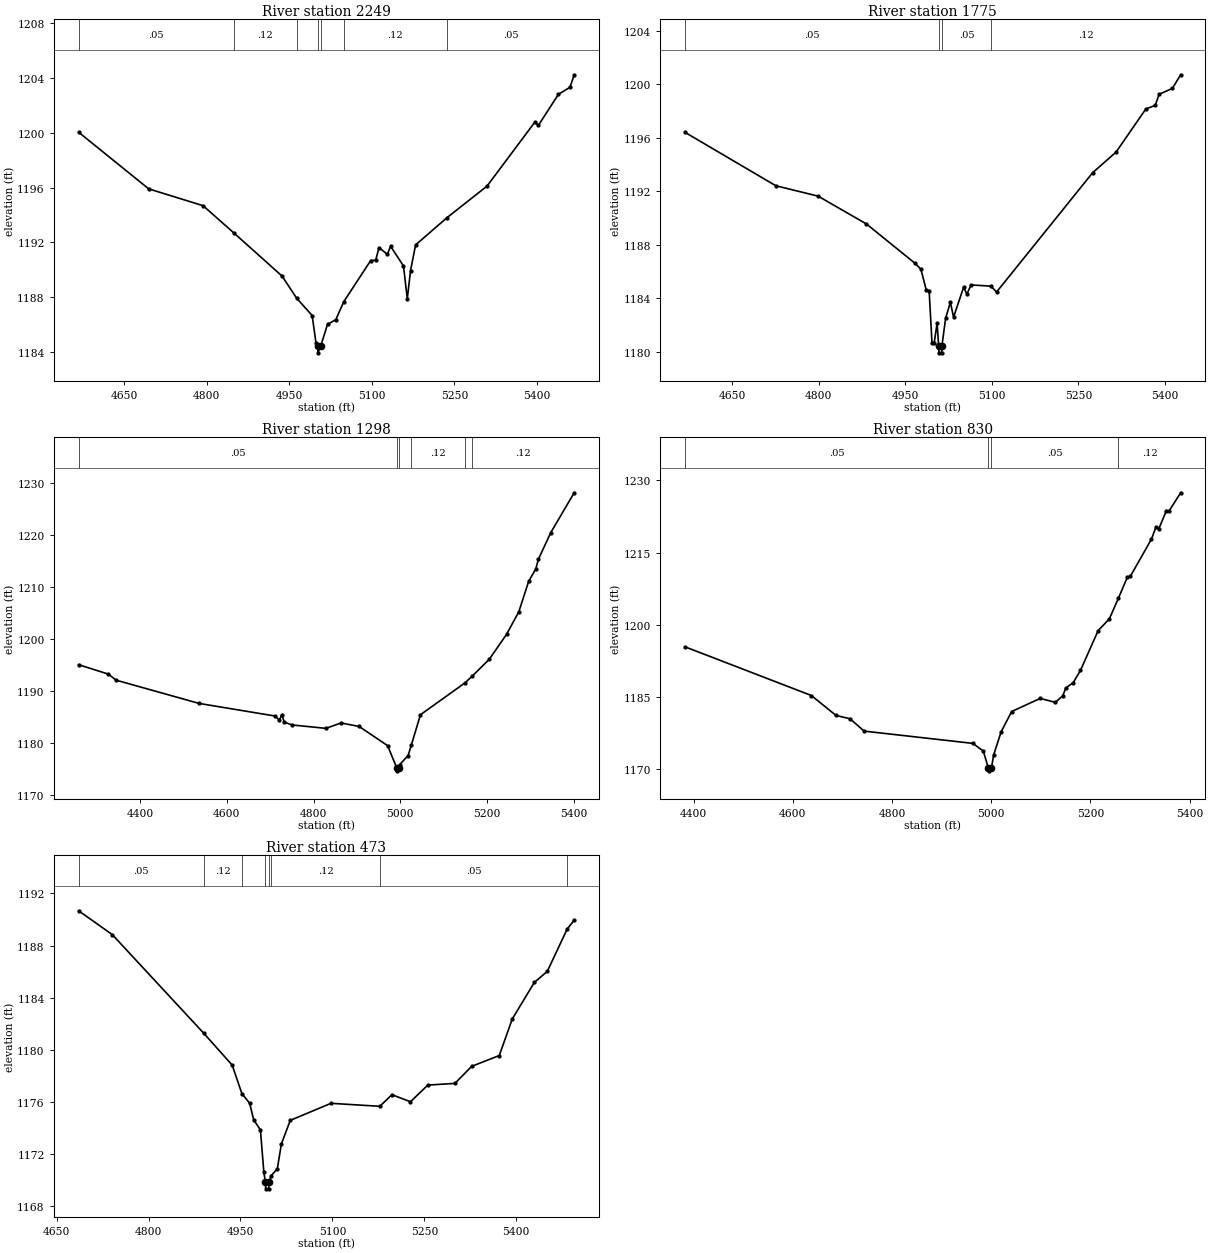
Type RM Length L Ch R = 1,2249,474,474,474
BEGIN DESCRIPTION:
LITTLE LLANO 022 5.0
END DESCRIPTION:
XS GIS Cut Line= 3
      2830405.70     10216203.14      2830550.50     10216611.00
      2830805.66     10217003.08
#Sta/Elev= 30
  4567.2 1200.05  4694.5 1195.91  4793.3 1194.68  4849.5 1192.68  4937.0 1189.53
  4963.5 1187.91  4991.6 1186.65  4998.5 1184.66  5001.7 1184.42  5002.1 1183.92
  5007.2 1184.42  5019.5 1186.00  5034.7 1186.35  5049.1 1187.66  5098.0 1190.67
  5107.1 1190.69  5113.1 1191.62  5128.2 1191.12  5134.2 1191.71  5157.6 1190.27
  5164.5 1187.87  5170.4 1189.93  5179.6 1191.81  5236.6 1193.80  5309.4 1196.11
  5396.2 1200.78  5402.9 1200.56  5439.2 1202.82  5460.3 1203.34  5467.8 1204.25
#Mann=7,-1,0
  4567.2    0.05       0  4849.5    0.12       0  4963.5    0.05       0
  5001.7    0.05       0  5007.2    0.05       0  5049.1    0.12       0
  5236.6    0.05       0
Bank Sta=5001.7,5007.2
Exp/Cntr=0.3,0.1

Type RM Length L Ch R = 1,1775,477,477,477
BEGIN DESCRIPTION:
LITTLE LLANO 022 4.0
END DESCRIPTION:
XS GIS Cut Line= 3
      2830355.68     10216303.11      2830227.75     10216715.00
      2830405.70     10217103.15
#Sta/Elev= 30
  4568.7 1196.39  4725.8 1192.40  4799.1 1191.62  4882.8 1189.54  4966.6 1186.61
  4977.1 1186.16  4986.2 1184.63  4991.4 1184.54  4996.4 1180.60  5000.0 1180.60
  5005.2 1182.12  5007.9 1180.40  5008.4 1179.90  5013.1 1179.90  5013.5 1180.40
  5019.9 1182.48  5028.2 1183.68  5033.7 1182.57  5051.2 1184.82  5056.7 1184.28
  5063.9 1184.98  5098.4 1184.89  5108.2 1184.45  5274.7 1193.38  5315.2 1194.92
  5366.7 1198.14  5383.0 1198.41  5389.7 1199.24  5412.7 1199.68  5427.0 1200.70
#Mann=4,-1,0
  4568.7    0.05       0  5007.9    0.05       0  5013.5    0.05       0
  5098.4    0.12       0
Bank Sta=5007.9,5013.5
Exp/Cntr=0.3,0.1

Type RM Length L Ch R = 1,1298,468,468,468
BEGIN DESCRIPTION:
LITTLE LLANO 022 3.0
END DESCRIPTION:
XS GIS Cut Line= 3
      2829705.68     10216353.09      2829983.25     10217041.00
      2830155.70     10217403.14
#Sta/Elev= 30
  4258.2 1195.12  4326.7 1193.31  4344.5 1192.15  4536.0 1187.68  4711.1 1185.26
  4721.2 1184.46  4726.6 1185.49  4732.7 1184.08  4750.7 1183.54  4828.6 1182.89
  4863.5 1183.93  4905.2 1183.25  4970.9 1179.56  4992.2 1175.23  4992.7 1174.73
  4997.8 1175.23  4998.4 1175.91  5018.1 1177.66  5025.7 1179.74  5046.6 1185.51
  5148.7 1191.59  5165.6 1192.89  5205.3 1196.16  5245.2 1200.96  5273.4 1205.28
  5296.1 1211.12  5312.5 1213.51  5318.8 1215.41  5347.1 1220.49  5401.1 1228.14
#Mann=6,-1,0
  4258.2    0.05       0  4992.2    0.05       0  4997.8    0.05       0
  5025.7    0.12       0  5148.7    0.05       0  5165.6    0.12       0
Bank Sta=4992.2,4997.8
Exp/Cntr=0.3,0.1

Type RM Length L Ch R = 1,830,357,357,357
BEGIN DESCRIPTION:
LITTLE LLANO 022 2.0
END DESCRIPTION:
XS GIS Cut Line= 3
      2829205.69     10216903.12      2829634.25     10217347.00
      2829955.65     10217553.09
#Sta/Elev= 30
  4383.0 1195.44  4637.5 1185.34  4687.2 1181.20  4715.5 1180.51  4743.8 1177.95
  4963.0 1175.40  4984.1 1173.80  4994.5 1170.20  4995.0 1169.70  5000.3 1170.20
  5004.9 1173.01  5020.1 1177.83  5041.2 1182.01  5098.7 1184.74  5129.1 1183.92
  5144.3 1185.28  5150.2 1186.89  5165.4 1188.02  5179.9 1190.55  5215.5 1198.81
  5238.1 1201.25  5256.4 1205.55  5274.5 1209.92  5280.4 1210.08  5322.7 1217.76
  5332.0 1220.27  5337.9 1219.97  5353.1 1223.72  5359.0 1223.73  5381.8 1227.43
#Mann=4,-1,0
  4383.0    0.05       0  4994.5    0.05       0  5000.3    0.05       0
  5256.4    0.12       0
Bank Sta=4994.5,5000.3
Exp/Cntr=0.3,0.1

Type RM Length L Ch R = 1,473,0,0,0
BEGIN DESCRIPTION:
LITTLE LLANO 022 1.0
END DESCRIPTION:
XS GIS Cut Line= 3
      2829155.68     10217053.09      2829285.50     10217339.00
      2829555.71     10217753.15
#Sta/Elev= 30
  4686.0 1190.67  4740.9 1188.84  4890.0 1181.27  4936.6 1178.81  4952.3 1176.63
  4965.1 1175.88  4971.6 1174.61  4982.6 1173.84  4988.2 1170.57  4990.8 1169.81
  4991.3 1169.31  4996.1 1169.31  4996.6 1169.81  5000.1 1170.31  5010.2 1170.86
  5016.8 1172.76  5031.3 1174.57  5097.7 1175.88  5177.3 1175.65  5197.2 1176.54
  5227.4 1176.00  5255.7 1177.28  5299.9 1177.41  5327.3 1178.72  5372.3 1179.55
  5393.4 1182.35  5429.6 1185.17  5450.7 1186.02  5482.9 1189.25  5494.5 1189.95
#Mann=8,-1,0
  4686.0    0.05       0  4890.0    0.12       0  4952.3    0.05       0
  4990.8    0.03       0  4996.6    0.05       0  5000.1    0.12       0
  5177.3    0.05       0  5482.9    0.12       0
Bank Sta=4990.8,4996.6
Exp/Cntr=0.3,0.1

Chan Stop Cuts=-1