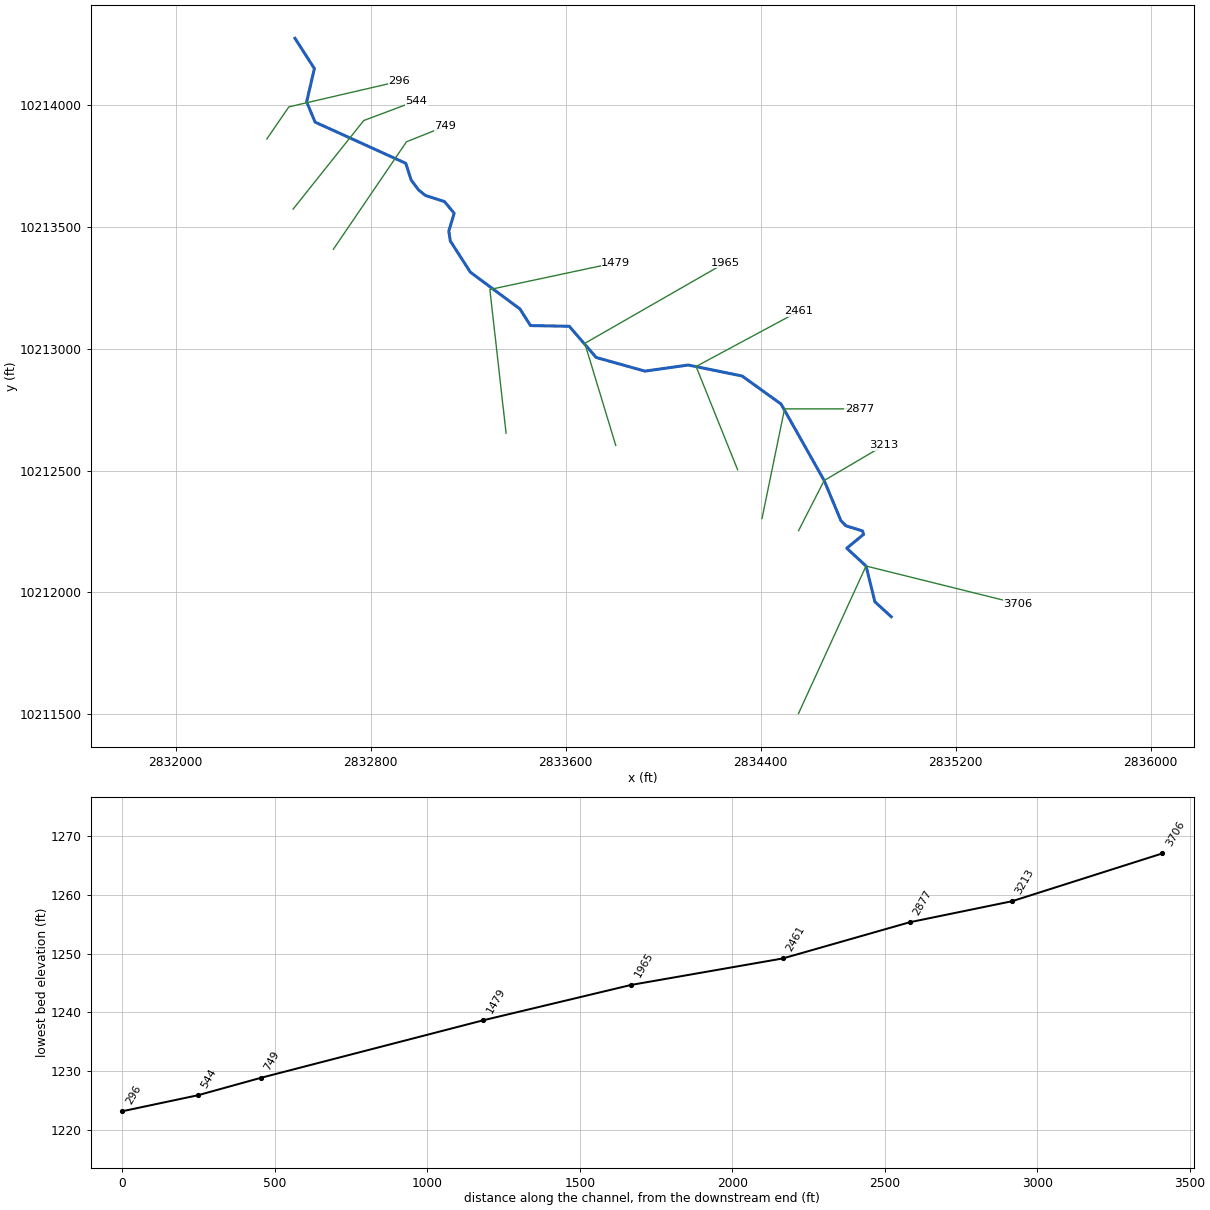
--- LITTLE LLANO 023.prj (project) ---

Proj Title=LITTLE LLANO 023 Base Level Engineering
Current Plan=p01
Default Exp/Contr=0.3,0.1
English Units
Geom File=g01
Flow File=f01
Plan File=p01
Y Axis Title=Elevation
X Axis Title(PF)=Main Channel Distance
X Axis Title(XS)=Station
BEGIN DESCRIPTION:
LITTLE LLANO 023
END DESCRIPTION:
DSS Export Rating Curves= 0
DSS Export Rating Curve Sorted= 0
DSS Export Volume Flow Curves= 0
DXF OffsetX= 0
DXF OffsetY= 0
DXF ScaleX= 1
DXF ScaleY= 10

--- LITTLE LLANO 023.p01 (plan) ---

Plan Title=Multiple Run
Short Identifier=Multiple
Geom File=g01
Flow File=f01
Subcritical Flow
K Sum by GR= 0
Std Step Tol= 0.01
Critical Tol= 0.01
Num of Std Step Trials= 20
Max Error Tol= 0.3
Flow Tol Ratio= 0.001
Split Flow NTrial= 30
Split Flow Tol= 0.02
Split Flow Ratio= 0.02
Log Output Level= 0
Friction Slope Method= 1
Unsteady Friction Slope Method= 2
Unsteady Bridges Friction Slope Method= 1
Parabolic Critical Depth
Global Vel Dist=  1 , 1 , 1
Global Log Level= 0
CheckData=True
Encroach Param= -1, 0, 0, 0
BEGIN DESCRIPTION:
Multiple Run
END DESCRIPTION:

--- LITTLE LLANO 023.f01 (steady flow) ---

Flow Title=Multiple
Number of Profiles=7
Profile Names=10-year,25-year,50-year,1pct_min,100-year,1pct_plu,500-year
River Rch & RM= LITTLE LLANO 023,Reach-1,3706
     216     336     799     678    1127    1875    1703
Boundary for River Rch & Prof#=LITTLE LLANO 023,Reach-1,1
Up Type=0
Dn Type=3
Dn Slope=0.005
Boundary for River Rch & Prof#=LITTLE LLANO 023,Reach-1,2
Up Type=0
Dn Type=3
Dn Slope=0.005
Boundary for River Rch & Prof#=LITTLE LLANO 023,Reach-1,3
Up Type=0
Dn Type=3
Dn Slope=0.005
Boundary for River Rch & Prof#=LITTLE LLANO 023,Reach-1,4
Up Type=0
Dn Type=3
Dn Slope=0.005
Boundary for River Rch & Prof#=LITTLE LLANO 023,Reach-1,5
Up Type=0
Dn Type=3
Dn Slope=0.005
Boundary for River Rch & Prof#=LITTLE LLANO 023,Reach-1,6
Up Type=0
Dn Type=3
Dn Slope=0.005
Boundary for River Rch & Prof#=LITTLE LLANO 023,Reach-1,7
Up Type=0
Dn Type=3
Dn Slope=0.005

--- LITTLE LLANO 023.g01 (geometry) ---

Geom Title=Existing Conditions
Program Version=4.10

River Reach=LITTLE LLANO 023,Reach-1
Reach XY= 30
      2834935.75       10211900.        2834869.       10211961.
       2834832.5       10212108.       2834753.5       10212181.
       2834822.5       10212238.      2834818.25       10212252.
        2834750.       10212273.       2834729.5       10212294.
      2834660.75       10212459.      2834483.75       10212773.
        2834324.       10212888.        2834103.       10212933.
       2833925.5       10212908.      2833725.25       10212964.
        2833615.       10213092.      2833455.75       10213095.
      2833412.75       10213163.      2833209.25       10213314.
        2833127.       10213442.      2833120.75       10213483.
      2833142.75       10213556.        2833103.       10213604.
      2833024.75       10213629.       2832996.5       10213652.
       2832966.5       10213692.      2832944.25       10213761.
      2832572.25       10213930.       2832537.5       10214013.
      2832569.25       10214150.      2832489.75       10214274.

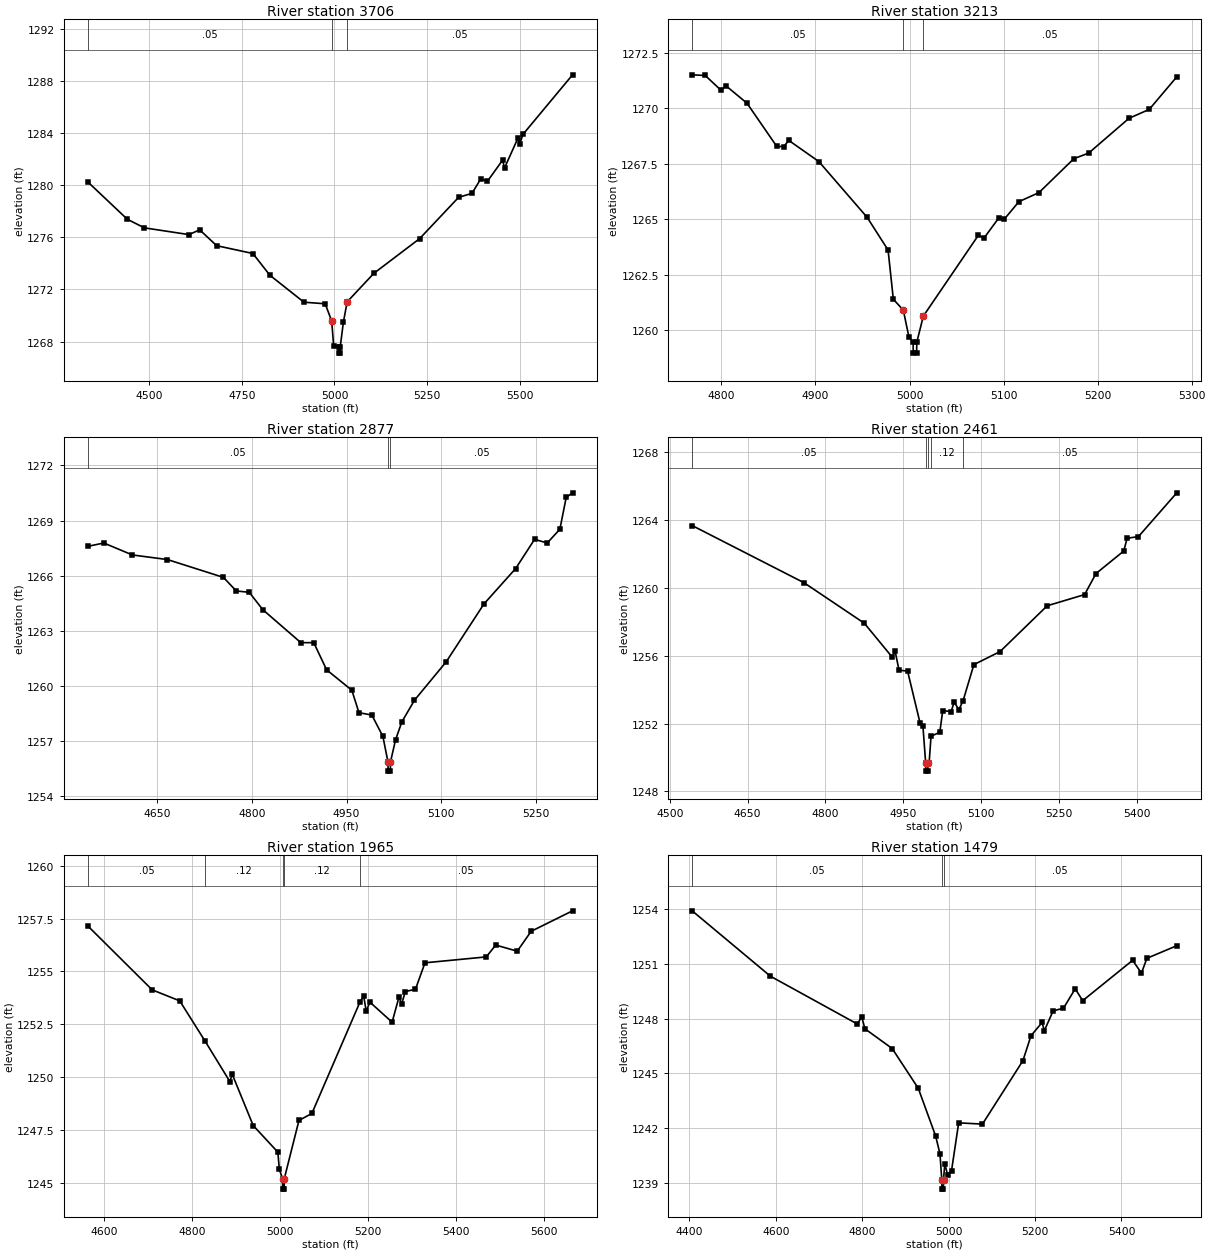
Type RM Length L Ch R = 1 ,3706    ,493,493,493
BEGIN DESCRIPTION:
LITTLE LLANO 023 7.0
END DESCRIPTION:
XS GIS Cut Line= 3
      2834555.69     10211503.13       2834832.5       10212108.
      2835455.64     10211953.12
#Sta/Elev= 30
  4334.8 1280.25  4441.1 1277.39  4487.1 1276.73  4607.7 1276.21  4636.2 1276.58
  4682.2 1275.36  4779.8 1274.76  4825.8 1273.09  4917.6 1271.02  4974.9  1270.9
  4992.4 1269.58  4997.8 1267.66  5011.6 1267.61  5011.8 1267.11  5015.3 1267.11
  5015.6 1267.61  5023.9 1269.47  5034.2 1271.05  5106.3 1273.24    5230 1275.91
  5334.7 1279.07  5370.9 1279.38  5394.8  1280.5  5412.2 1280.29  5453.5 1281.93
  5458.7 1281.33  5494.9 1283.62    5500  1283.2  5508.2  1283.9  5642.1 1288.48
#Mann= 3 , 0 , 0
  4334.8     .05       0  4992.4     .05       0  5034.2     .05       0
Bank Sta=4992.4,5034.2
XS Rating Curve= 0 ,0
Exp/Cntr=0.3,0.1

Type RM Length L Ch R = 1 ,3213    ,336,336,336
BEGIN DESCRIPTION:
LITTLE LLANO 023 6.0
END DESCRIPTION:
XS GIS Cut Line= 3
      2834555.71     10212253.15      2834660.75       10212459.
       2834905.7     10212603.12
#Sta/Elev= 30
  4768.9 1271.51  4782.8 1271.48  4799.4 1270.82    4805 1271.01  4827.2 1270.23
  4858.7 1268.29  4866.1 1268.27  4871.7 1268.55  4903.6  1267.6    4955 1265.08
  4977.2 1263.61  4982.8 1261.39  4993.4  1260.9  4999.4 1259.68  5003.8 1259.46
    5004 1258.96  5007.5 1258.96  5007.8 1259.46  5014.7 1260.63  5073.3 1264.28
  5079.1 1264.14  5094.8 1265.05  5100.6 1264.99  5116.3 1265.79  5137.7  1266.2
  5174.8 1267.73  5190.5 1267.98  5233.4 1269.55  5254.9 1269.95  5284.2 1271.42
#Mann= 3 , 0 , 0
  4768.9     .05       0  4993.4     .05       0  5014.7     .05       0
Bank Sta=4993.4,5014.7
XS Rating Curve= 0 ,0
Exp/Cntr=0.3,0.1

Type RM Length L Ch R = 1 ,2877    ,416,416,416
BEGIN DESCRIPTION:
LITTLE LLANO 023 5.0
END DESCRIPTION:
XS GIS Cut Line= 3
      2834405.69     10212303.12      2834498.25       10212753.
      2834805.65     10212753.11
#Sta/Elev= 30
  4540.7  1267.6  4565.9 1267.78  4611.1 1267.13  4666.5 1266.88  4755.1 1265.91
  4775.5 1265.17  4795.9  1265.1  4817.5 1264.15  4877.6 1262.36    4898 1262.36
  4918.4 1260.88  4958.3 1259.77  4969.5 1258.55  4989.9 1258.42  5007.4 1257.26
  5015.4 1255.87  5015.7 1255.37  5019.2 1255.37  5019.4 1255.87  5027.4 1257.07
  5037.4 1258.05  5057.4 1259.23  5107.4 1261.31  5167.4 1264.47  5217.4 1266.39
  5247.4 1267.98  5267.4 1267.78  5287.4 1268.53  5297.4 1270.26  5307.4 1270.51
#Mann= 3 ,-1 , 0
  4540.7     .05       0  5015.4     .05       0  5019.4     .05       0
Bank Sta=5015.4,5019.4
XS Rating Curve= 0 ,0
Exp/Cntr=0.3,0.1

Type RM Length L Ch R = 1 ,2461    ,496,496,496
BEGIN DESCRIPTION:
LITTLE LLANO 023 4.0
END DESCRIPTION:
XS GIS Cut Line= 3
       2834305.7     10212503.08      2834135.25       10212927.
       2834555.7     10213153.12
#Sta/Elev= 30
  4543.1 1263.68  4758.7 1260.31    4875 1257.92  4928.8 1255.92  4934.2  1256.3
  4941.9 1255.15  4958.4  1255.1  4982.5 1252.03  4987.9 1251.89  4993.2  1249.7
  4993.5  1249.2    4997  1249.2  4997.2  1249.7    5000  1249.7  5003.6 1251.26
  5020.5 1251.49  5026.2 1252.77  5042.4 1252.71  5048.1 1253.27  5057.3 1252.83
  5065.3 1253.34  5086.2 1255.48  5136.7 1256.25  5227.6 1258.95  5299.7 1259.61
  5321.6 1260.85  5375.2 1262.18  5381.6 1262.93  5403.5 1263.03  5477.4 1265.61
#Mann= 5 ,-1 , 0
  4543.1     .05       0  4993.2     .05       0  4997.2     .05       0
  5003.6     .12       0  5065.3     .05       0
Bank Sta=4993.2,4997.2
XS Rating Curve= 0 ,0
Exp/Cntr=0.3,0.1

Type RM Length L Ch R = 1 ,1965    ,486,486,486
BEGIN DESCRIPTION:
LITTLE LLANO 023 3.0
END DESCRIPTION:
XS GIS Cut Line= 3
      2833805.68     10212603.11      2833678.75       10213022.
      2834255.69     10213353.11
#Sta/Elev= 30
  4562.3 1257.15  4708.6 1254.13  4771.3 1253.61  4829.4 1251.69  4885.4 1249.79
  4890.7 1250.14  4938.5 1247.71  4994.6 1246.45    4998 1245.63  5005.3  1245.2
  5005.5  1244.7    5009  1244.7  5009.3  1245.2  5042.6 1247.95    5072 1248.28
  5181.4 1253.55  5189.9 1253.84  5195.7 1253.12    5204 1253.55  5254.6  1252.6
  5270.4  1253.8  5276.2 1253.45  5284.7 1254.05  5307.8 1254.16  5329.4 1255.41
  5468.9 1255.69  5490.5 1256.25  5539.4 1255.96    5571  1256.9  5665.2 1257.87
#Mann= 5 ,-1 , 0
  4562.3     .05       0  4829.4     .12       0  5005.3     .07       0
  5009.3     .12       0  5181.4     .05       0
Bank Sta=5005.3,5009.3
XS Rating Curve= 0 ,0
Exp/Cntr=0.3,0.1

Type RM Length L Ch R = 1 ,1479    ,730,730,730
BEGIN DESCRIPTION:
LITTLE LLANO 023 2.0
END DESCRIPTION:
XS GIS Cut Line= 3
      2833355.68     10212653.13      2833289.25       10213243.
      2833805.64      10213353.1
#Sta/Elev= 30
  4406.4  1253.9  4587.5 1250.32  4788.8  1247.7  4798.8  1248.1  4806.2 1247.44
  4869.3 1246.36  4929.7 1244.18  4969.9 1241.57    4980 1240.58  4984.1 1239.16
  4984.4 1238.66  4987.9 1238.66  4988.1 1239.16  4991.1 1240.05  4997.5 1239.45
  5006.6 1239.66  5023.2 1242.29  5078.2 1242.22  5171.8 1245.69  5190.6 1247.06
  5216.3 1247.79  5221.4 1247.33  5241.7 1248.42  5265.8 1248.57  5292.9 1249.63
  5310.2 1248.98  5425.8 1251.19  5446.2 1250.49  5458.8  1251.3    5528 1251.99
#Mann= 3 ,-1 , 0
  4406.4     .05       0  4984.1     .03       0  4988.1     .05       0
Bank Sta=4984.1,4988.1
XS Rating Curve= 0 ,0
Exp/Cntr=0.3,0.1

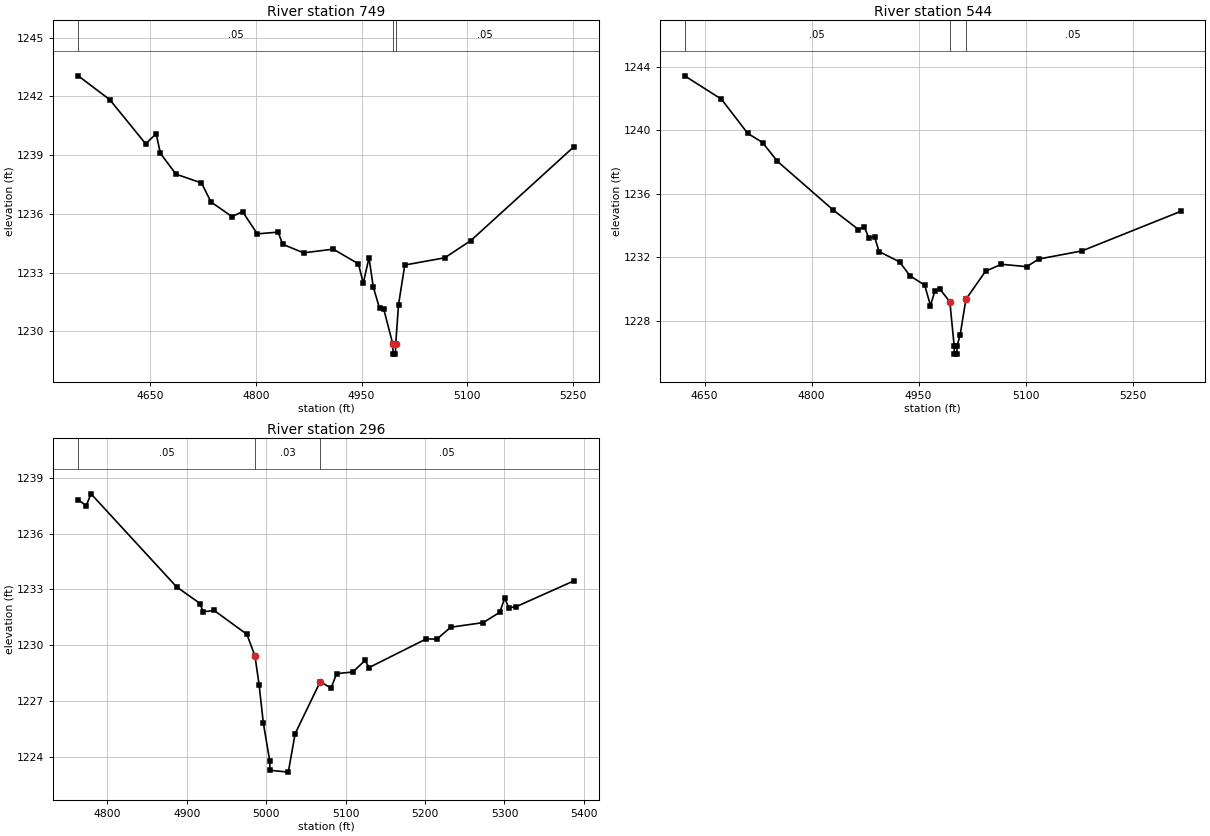
Type RM Length L Ch R = 1 ,749     ,205,205,205
BEGIN DESCRIPTION:
Mapping XS 524b9864
END DESCRIPTION:
XS GIS Cut Line= 3
      2832647.22      10213408.3      2832947.23     10213849.48
      2833106.05      10213912.8
#Sta/Elev= 30
  4547.5 1243.05  4592.4 1241.83  4643.3 1239.58  4658.2 1240.09  4664.3 1239.09
  4686.3 1238.03  4722.6 1237.58  4736.1 1236.61    4766 1235.86  4780.9 1236.12
  4801.9 1234.98  4831.5 1235.07  4837.9 1234.45  4867.7 1234.01  4909.7  1234.2
  4945.6 1233.45  4952.4 1232.46  4960.6 1233.76  4966.6 1232.27  4975.5 1231.19
  4981.5 1231.14  4994.5 1229.34  4994.7 1228.84  4998.2 1228.84  4998.5 1229.34
  5002.5 1231.36  5011.4 1233.39  5068.3 1233.76  5105.3 1234.64    5252 1239.44
#Mann= 3 ,-1 , 0
  4547.5     .05       0  4994.5     .05       0  4998.5     .05       0
Bank Sta=4994.5,4998.5
XS Rating Curve= 0 ,0
Exp/Cntr=0.3,0.1

Type RM Length L Ch R = 1 ,544     ,248,248,248
BEGIN DESCRIPTION:
Mapping XS e8a73547
END DESCRIPTION:
XS GIS Cut Line= 3
       2832482.2     10213573.36      2832771.81     10213936.67
      2832987.71     10214017.63
#Sta/Elev= 30
  4622.2 1243.42  4673.7 1241.95  4710.5  1239.8  4731.3 1239.22  4752.1 1238.04
  4830.6 1234.96  4865.8 1233.74  4873.9 1233.92  4880.2 1233.21  4888.3 1233.29
  4894.7 1232.35  4923.5  1231.7  4937.9 1230.83  4958.7 1230.23  4966.7 1228.95
  4973.1 1229.89    4980 1229.98  4993.9 1229.19    5000 1226.39  5000.2 1225.89
  5003.7 1225.89    5004 1226.39  5008.4 1227.11  5016.4 1229.34  5043.9 1231.11
    5066 1231.55  5101.6  1231.4  5118.5 1231.88    5179 1232.39  5317.4 1234.88
#Mann= 3 , 0 , 0
  4622.2     .05       0  4993.9     .05       0  5016.4     .05       0
Bank Sta=4993.9,5016.4
XS Rating Curve= 0 ,0
Exp/Cntr=0.3,0.1

Type RM Length L Ch R = 1 ,296     ,0,0,0
BEGIN DESCRIPTION:
LITTLE LLANO 023 1.0
END DESCRIPTION:
XS GIS Cut Line= 3
      2832374.25     10213860.89      2832464.56     10213992.72
      2832917.08     10214097.55
#Sta/Elev= 30
  4763.4 1237.82  4773.5  1237.5  4779.5 1238.14  4887.3 1233.13    4917 1232.23
  4920.4 1231.79  4934.6 1231.86  4975.7 1230.58  4985.9 1229.41  4991.2 1227.83
  4996.4 1225.81  5004.5 1223.76  5004.7 1223.26 5027.85 1223.16 5036.48 1225.23
  5068.1 1228.03  5081.7 1227.68  5088.6 1228.46  5109.1 1228.55  5124.4 1229.17
  5129.6 1228.79  5201.5 1230.33  5214.9 1230.32  5232.3 1230.96  5273.4 1231.21
  5293.9 1231.76  5300.3 1232.52  5305.4 1232.01  5314.4 1232.06  5387.7 1233.46
#Mann= 3 , 0 , 0
  4763.4     .05       0  4985.9     .03       0  5068.1     .05       0
Bank Sta=4985.9,5068.1
XS Rating Curve= 0 ,0
Exp/Cntr=0.3,0.1

Chan Stop Cuts=-1
Use User Specified Reach Order=0
Composite Channel Slope=5