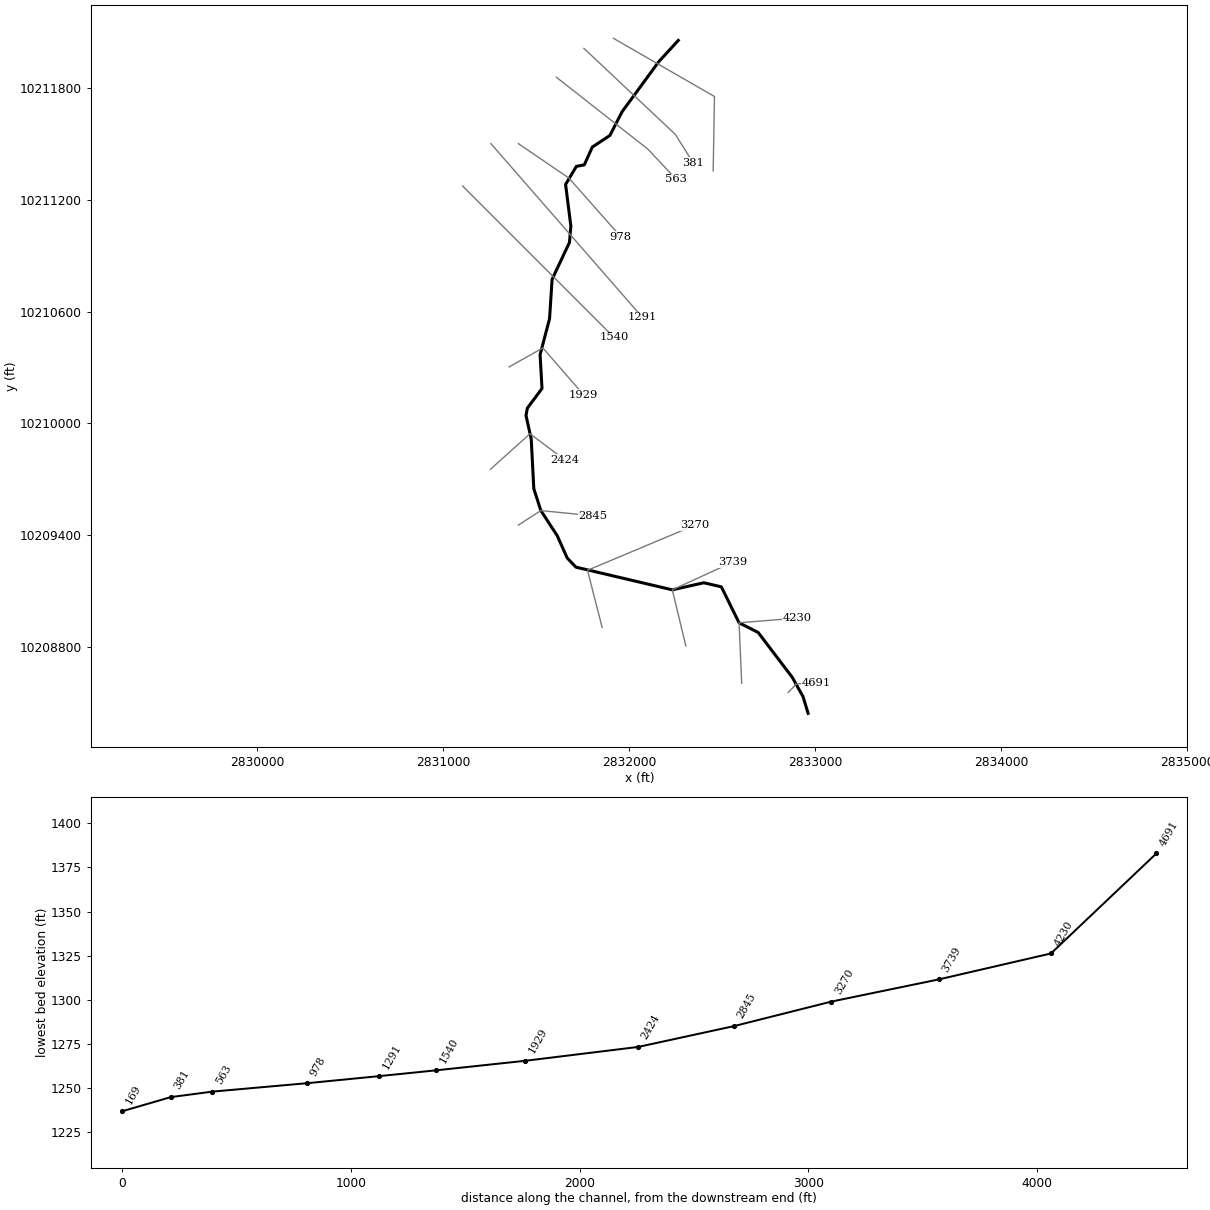
--- LITTLE LLANO 025.prj (project) ---

Proj Title=LITTLE LLANO 025 Base Level Engineering
Current Plan=p01
Default Exp/Contr=0.3,0.1
English Units
Geom File=g01
Flow File=f01
Plan File=p01
Y Axis Title=Elevation
X Axis Title(PF)=Main Channel Distance
X Axis Title(XS)=Station
BEGIN DESCRIPTION:
LITTLE LLANO 025
END DESCRIPTION:
DSS Export Rating Curves= 0
DSS Export Rating Curve Sorted= 0
DSS Export Volume Flow Curves= 0
DXF OffsetX= 0
DXF OffsetY= 0
DXF ScaleX= 1
DXF ScaleY= 10

--- LITTLE LLANO 025.p01 (plan) ---

Plan Title=Multiple Run
Short Identifier=Multiple
Geom File=g01
Flow File=f01
Subcritical Flow
K Sum by GR= 0
Std Step Tol= 0.01
Critical Tol= 0.01
Num of Std Step Trials= 20
Max Error Tol= 0.3
Flow Tol Ratio= 0.001
Split Flow NTrial= 30
Split Flow Tol= 0.02
Split Flow Ratio= 0.02
Log Output Level= 0
Friction Slope Method= 1
Unsteady Friction Slope Method= 2
Unsteady Bridges Friction Slope Method= 1
Parabolic Critical Depth
Global Vel Dist=  1 , 1 , 1
Global Log Level= 0
CheckData=True
Encroach Param= -1, 0, 0, 0
BEGIN DESCRIPTION:
Multiple Run
END DESCRIPTION:

--- LITTLE LLANO 025.f01 (steady flow) ---

Flow Title=Multiple
Number of Profiles=7
Profile Names=10-year,25-year,50-year,1pct_min,100-year,1pct_plu,500-year
River Rch & RM= LITTLE LLANO 025,Reach-1,4691
     153     232     466     397     638    1027     949
Boundary for River Rch & Prof#=LITTLE LLANO 025,Reach-1,1
Up Type=0
Dn Type=3
Dn Slope=0.005
Boundary for River Rch & Prof#=LITTLE LLANO 025,Reach-1,2
Up Type=0
Dn Type=3
Dn Slope=0.005
Boundary for River Rch & Prof#=LITTLE LLANO 025,Reach-1,3
Up Type=0
Dn Type=3
Dn Slope=0.005
Boundary for River Rch & Prof#=LITTLE LLANO 025,Reach-1,4
Up Type=0
Dn Type=3
Dn Slope=0.005
Boundary for River Rch & Prof#=LITTLE LLANO 025,Reach-1,5
Up Type=0
Dn Type=3
Dn Slope=0.005
Boundary for River Rch & Prof#=LITTLE LLANO 025,Reach-1,6
Up Type=0
Dn Type=3
Dn Slope=0.005
Boundary for River Rch & Prof#=LITTLE LLANO 025,Reach-1,7
Up Type=0
Dn Type=3
Dn Slope=0.005

--- LITTLE LLANO 025.g01 (geometry) ---

Geom Title=Existing Conditions
Program Version=4.10

River Reach=LITTLE LLANO 025,Reach-1
Reach XY= 30
      2832962.75       10208441.       2832935.5       10208531.
        2832878.       10208634.      2832694.25       10208876.
       2832591.5       10208928.       2832496.5       10209121.
      2832402.25       10209143.      2832232.75       10209105.
      2831714.75       10209227.        2831668.       10209276.
      2831614.25       10209396.      2831526.25       10209531.
       2831488.5       10209648.       2831474.5       10209916.
       2831446.5       10210042.        2831454.       10210082.
       2831532.5       10210187.      2831522.25       10210369.
        2831573.       10210562.      2831586.75       10210774.
        2831680.       10210972.       2831687.5       10211060.
      2831659.25       10211284.      2831717.25       10211381.
      2831759.75       10211389.        2831803.       10211485.
      2831897.25       10211547.       2831962.5       10211674.
      2832160.25       10211944.        2832265.       10212058.

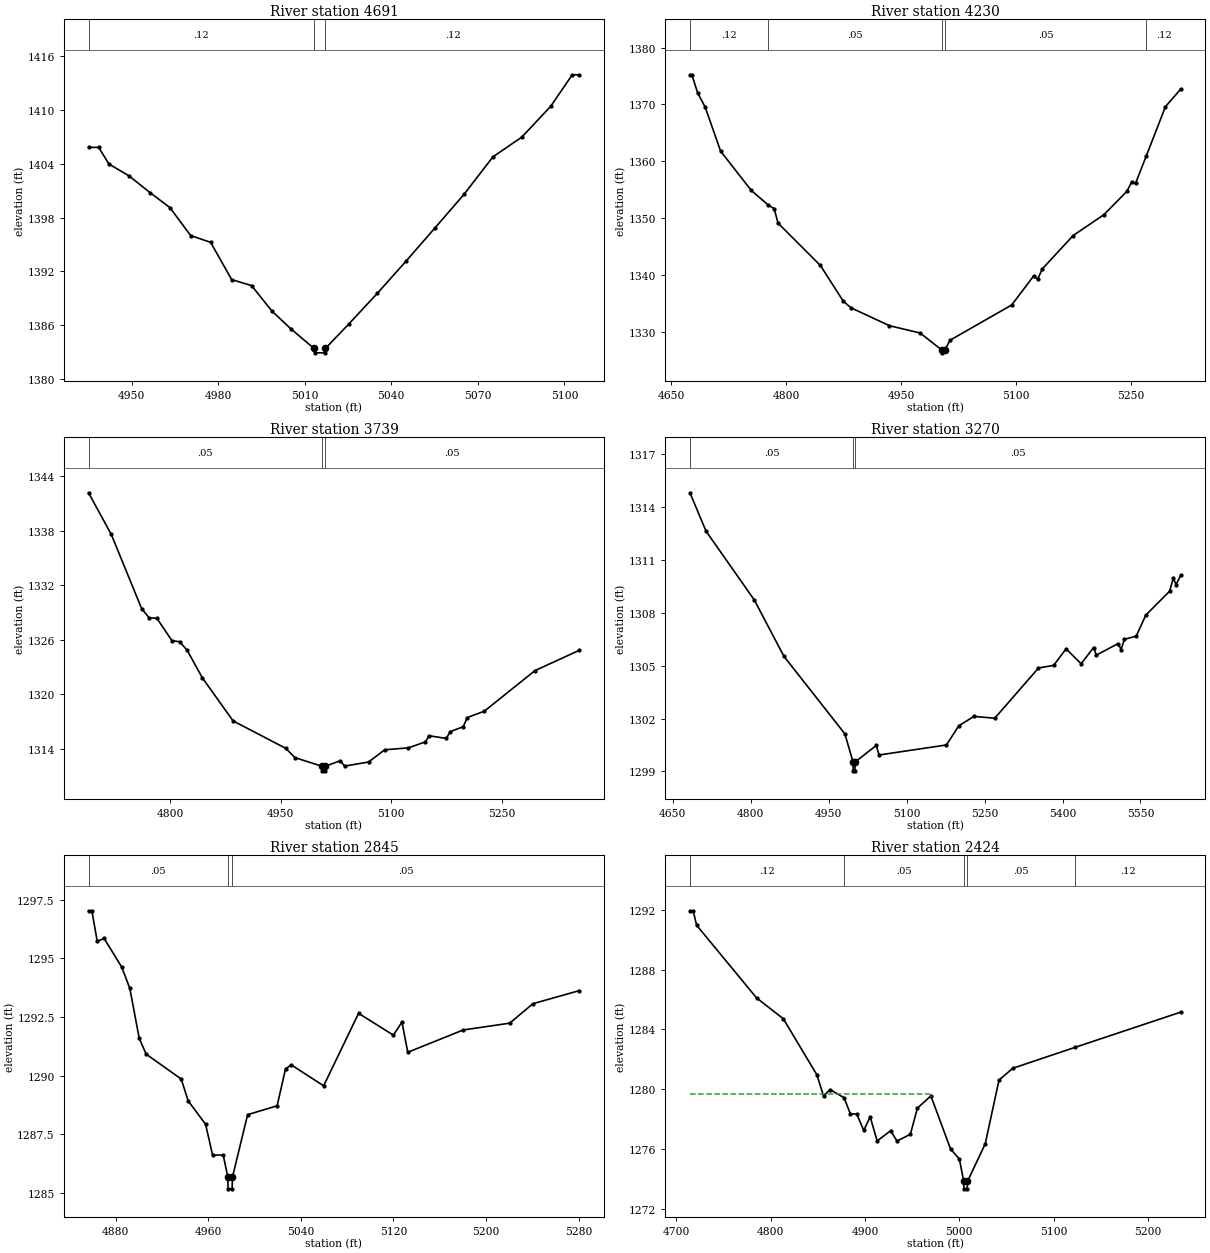
Type RM Length L Ch R = 1 ,4691    ,461,461,461
BEGIN DESCRIPTION:
LITTLE LLANO 025 10.0
END DESCRIPTION:
XS GIS Cut Line= 3
      2832855.66     10208553.08       2832900.5       10208600.
      2833005.65     10208603.11
#Sta/Elev= 26
  4935.1 1405.83  4938.6 1405.83  4942.2 1403.97  4949.1 1402.66  4956.4 1400.79
  4963.3 1399.11  4970.5 1395.99  4977.4 1395.24  4984.7 1391.08  4991.6 1390.41
  4998.7 1387.55  5005.2 1385.59  5013.2 1383.41  5013.4 1382.91  5016.9 1382.91
  5017.2 1383.41  5025.2  1386.1  5035.2 1389.56  5045.2 1393.17  5055.2 1396.87
  5065.2 1400.59  5075.2 1404.77  5085.2 1406.97  5095.2  1410.4  5102.7 1413.93
  5105.2 1413.93
#Mann= 3 ,-1 , 0
  4935.1     .12       0  5013.2     .07       0  5017.2     .12       0
Bank Sta=5013.2,5017.2
XS Rating Curve= 0 ,0
Exp/Cntr=0.3,0.1

Type RM Length L Ch R = 1 ,4230    ,491,491,491
BEGIN DESCRIPTION:
LITTLE LLANO 025 9.0
END DESCRIPTION:
XS GIS Cut Line= 3
      2832605.68     10208603.11       2832591.5       10208928.
       2832905.7     10208953.11
#Sta/Elev= 30
  4674.8 1375.22  4677.3 1375.22  4684.8 1372.06  4694.8 1369.49  4714.8 1361.78
  4754.9 1354.85  4776.9  1352.3  4784.7 1351.66  4789.7 1349.11    4845 1341.65
    4875 1335.33    4885 1334.19    4935 1331.05  4975.1 1329.76  5003.3 1326.77
  5003.6 1326.27  5007.3 1326.77  5014.2  1328.5  5094.5 1334.69  5123.2 1339.81
  5128.3 1339.23  5134.6 1341.07  5174.7 1346.92  5214.9  1350.6    5245 1354.74
  5251.2  1356.4  5256.2 1356.15  5270.2 1360.97  5295.1 1369.61  5315.2 1372.73
#Mann= 5 ,-1 , 0
  4674.8     .12       0  4776.9     .05       0  5003.3     .05       0
  5007.3     .05       0  5270.2     .12       0
Bank Sta=5003.3,5007.3
XS Rating Curve= 0 ,0
Exp/Cntr=0.3,0.1

Type RM Length L Ch R = 1 ,3739    ,469,469,469
BEGIN DESCRIPTION:
LITTLE LLANO 025 8.0
END DESCRIPTION:
XS GIS Cut Line= 3
      2832305.69     10208803.09      2832232.75       10209105.
       2832555.7     10209253.12
#Sta/Elev= 30
  4689.4 1342.19  4720.3  1337.6  4761.4 1329.44  4771.7 1328.41    4782 1328.38
  4802.6  1325.9  4812.9 1325.79  4823.2 1324.85  4843.7 1321.82  4885.5 1317.07
  4956.9 1314.05  4969.3 1313.03  5006.1 1312.07  5006.3 1311.57  5009.8 1311.57
  5010.1 1312.07  5031.1 1312.69  5036.6 1312.09  5069.2 1312.54  5091.2 1313.89
  5123.1  1314.1  5146.1 1314.75  5151.6 1315.43  5174.6 1315.14  5180.1 1315.89
  5197.6 1316.43  5203.1 1317.44  5226.1 1318.13    5295 1322.61  5355.3 1324.85
#Mann= 3 ,-1 , 0
  4689.4     .05       0  5006.1     .05       0  5010.1     .05       0
Bank Sta=5006.1,5010.1
XS Rating Curve= 0 ,0
Exp/Cntr=0.3,0.1

Type RM Length L Ch R = 1 ,3270    ,425,425,425
BEGIN DESCRIPTION:
LITTLE LLANO 025 7.0
END DESCRIPTION:
XS GIS Cut Line= 3
      2831855.68     10208903.13        2831777.       10209210.
      2832355.71     10209453.12
#Sta/Elev= 30
  4683.2 1314.82  4714.2 1312.64  4807.1 1308.73  4864.1 1305.53  4981.3 1301.13
    4997 1299.53  4997.3 1299.03  5000.8 1299.03    5001 1299.53  5041.6 1300.47
  5047.1 1299.93  5176.7  1300.5  5200.5 1301.59  5229.6 1302.12  5269.7 1302.02
  5353.8 1304.87    5383 1305.02  5406.8 1305.96  5435.9 1305.11  5459.7 1306.03
  5465.1  1305.6  5507.2 1306.26  5512.6 1305.92  5519.2  1306.5  5541.8 1306.68
  5560.2 1307.87    5606 1309.23  5613.1 1309.96  5618.5 1309.61  5627.7 1310.15
#Mann= 3 ,-1 , 0
  4683.2     .05       0    4997     .05       0    5001     .05       0
Bank Sta=4997,5001
XS Rating Curve= 0 ,0
Exp/Cntr=0.3,0.1

Type RM Length L Ch R = 1 ,2845    ,421,421,421
BEGIN DESCRIPTION:
LITTLE LLANO 025 6.0
END DESCRIPTION:
XS GIS Cut Line= 3
      2831405.71     10209453.13      2831526.25       10209531.
      2831805.66     10209503.11
#Sta/Elev= 30
  4856.5 1297.03  4859.4 1297.03    4864 1295.73    4870 1295.85  4885.2 1294.63
  4892.2 1293.72  4900.3  1291.6  4906.3 1290.92  4936.6 1289.86  4942.6 1288.93
  4957.7 1287.93  4963.7 1286.62  4972.9 1286.62  4976.9 1285.68  4977.1 1285.18
  4980.6 1285.18  4980.9 1285.68    4994 1288.34  5019.5 1288.72  5026.8  1290.3
  5031.8 1290.46  5059.7 1289.57  5089.9 1292.66    5120 1291.73  5127.4 1292.29
  5132.4    1291  5180.3 1291.95  5220.5 1292.24  5240.6 1293.07  5280.8 1293.63
#Mann= 3 ,-1 , 0
  4856.5     .05       0  4976.9     .05       0  4980.9     .05       0
Bank Sta=4976.9,4980.9
XS Rating Curve= 0 ,0
Exp/Cntr=0.3,0.1

Type RM Length L Ch R = 1 ,2424    ,495,495,495
BEGIN DESCRIPTION:
LITTLE LLANO 025 5.0
END DESCRIPTION:
XS GIS Cut Line= 3
      2831255.69     10209753.12        2831468.       10209944.
       2831655.7      10209803.1
#Sta/Elev= 30
  4714.5 1291.94  4717.9 1291.94  4721.6 1290.97  4785.1 1286.11  4813.5 1284.71
    4849 1280.96  4856.1 1279.54  4862.9 1279.97  4877.8 1279.43  4884.5 1278.35
  4891.3 1278.33  4898.7 1277.24  4905.5 1278.15  4912.9 1276.53  4927.1 1277.22
  4933.9 1276.53  4948.1 1276.98  4955.5 1278.73  4969.8 1279.55  4990.7 1275.99
    5000 1275.33  5004.6 1273.83  5004.8 1273.33  5008.3 1273.33  5008.6 1273.83
  5027.4 1276.34    5042 1280.61  5056.6  1281.4  5122.6  1282.8  5234.7 1285.16
#Mann= 5 ,-1 , 0
  4714.5     .12       0  4877.8     .05       0  5004.6     .05       0
  5008.6     .05       0  5122.6     .12       0
#XS Ineff= 2 , 0
         4970.15 1279.68
Permanent Ineff=
       F       F
Bank Sta=5004.6,5008.6
XS Rating Curve= 0 ,0
Exp/Cntr=0.3,0.1

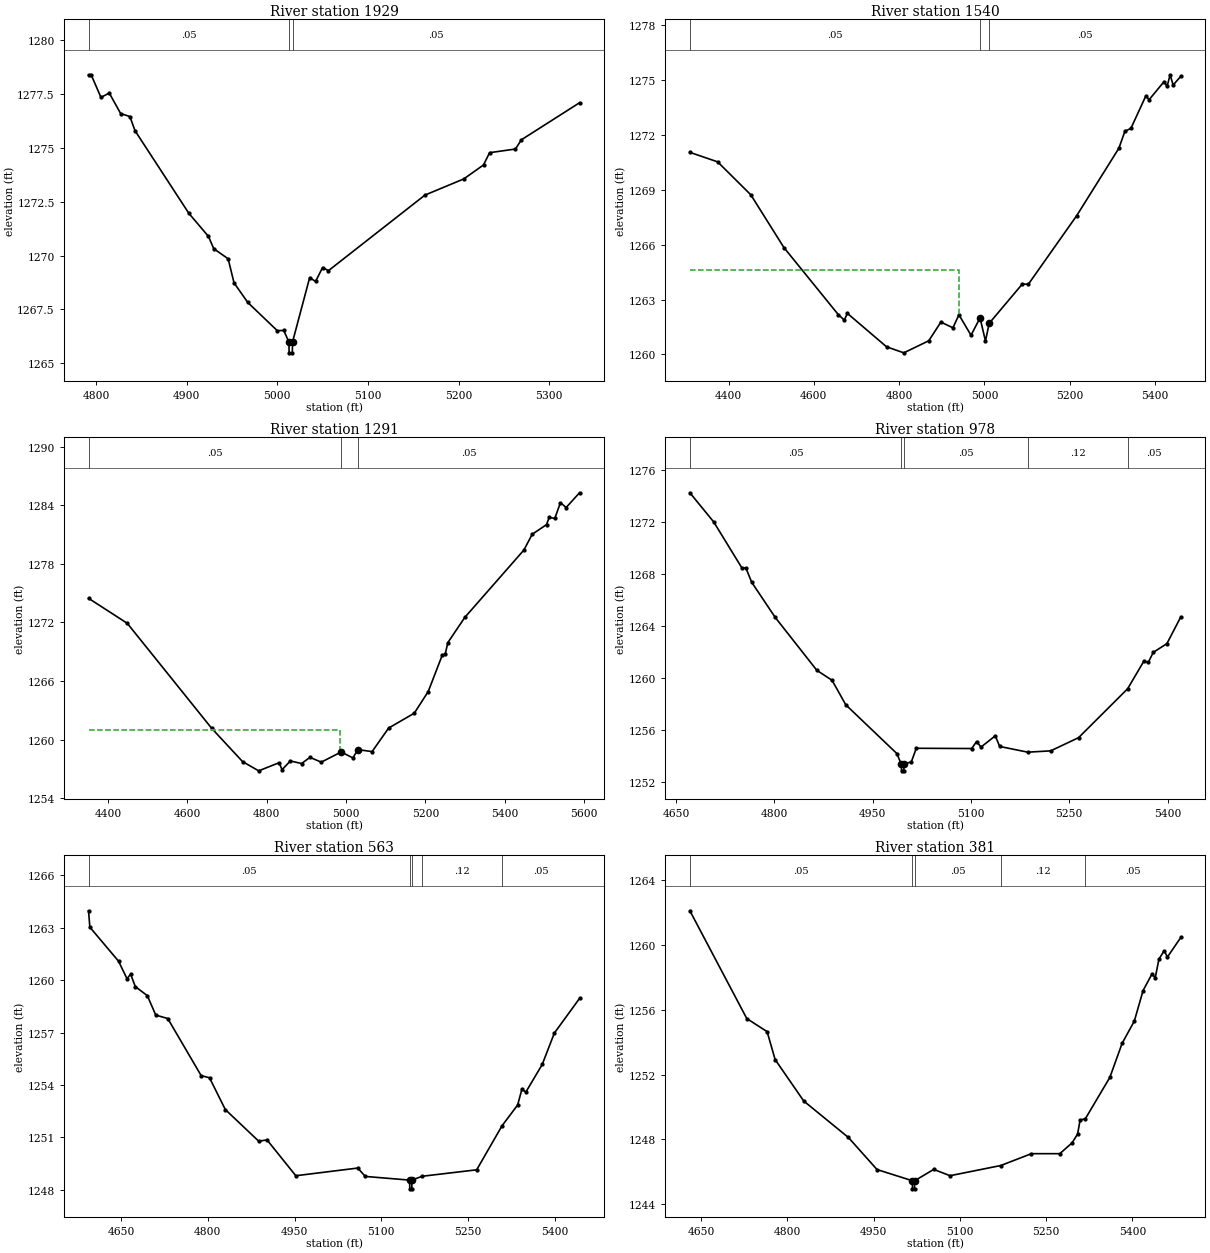
Type RM Length L Ch R = 1 ,1929    ,389,389,389
BEGIN DESCRIPTION:
LITTLE LLANO 025 4.0
END DESCRIPTION:
XS GIS Cut Line= 3
      2831355.68     10210303.11      2831537.25       10210405.
      2831755.68     10210153.12
#Sta/Elev= 30
  4791.8  1278.4  4794.7  1278.4  4805.5 1277.35  4814.7 1277.55  4827.2  1276.6
  4837.4 1276.46  4843.1  1275.8  4902.5 1271.96  4924.1 1270.89  4929.9 1270.32
  4945.8 1269.85  4952.3 1268.73  4967.5 1267.82    5000 1266.51  5007.2 1266.52
  5012.8 1265.98  5013.1 1265.48  5016.6 1265.48  5016.8 1265.98  5035.7 1268.97
  5042.3  1268.8  5049.9 1269.44  5056.5  1269.3  5162.9 1272.81  5205.7 1273.56
  5227.5 1274.21  5234.2 1274.78  5262.7 1274.95  5269.3 1275.38  5333.4  1277.1
#Mann= 3 ,-1 , 0
  4791.8     .05       0  5012.8     .05       0  5016.8     .05       0
Bank Sta=5012.8,5016.8
XS Rating Curve= 0 ,0
Exp/Cntr=0.3,0.1

Type RM Length L Ch R = 1 ,1540    ,249,249,249
BEGIN DESCRIPTION:
Mapping XS 3ab08502
END DESCRIPTION:
XS GIS Cut Line= 2
       2831105.9     10211275.33      2831919.71     10210461.52
#Sta/Elev= 30
  4309.4 1271.05  4374.5 1270.53  4452.2 1268.73    4530 1265.84  4657.3 1262.18
  4671.4 1261.88  4678.5 1262.25  4770.4 1260.42  4810.9 1260.09  4869.4 1260.75
  4897.7 1261.77    4926 1261.46  4940.1 1262.17  4968.4 1261.05  4989.6    1262
  5002.3 1260.73  5010.9  1261.7  5088.6 1263.85  5102.8 1263.84  5215.9 1267.58
  5314.9 1271.27  5329.1  1272.2  5343.2 1272.36  5378.5 1274.15  5385.6 1273.92
    5421 1274.92    5428 1274.65  5435.1 1275.29  5442.2 1274.73  5460.3 1275.21
#Mann= 3 , 0 , 0
  4309.4     .05       0  4989.6     .05       0  5010.9     .05       0
#XS Ineff= 2 , 0
         4939.29 1264.62
Permanent Ineff=
       F       F
Bank Sta=4989.6,5010.9
XS Rating Curve= 0 ,0
Exp/Cntr=0.5,0.3

Type RM Length L Ch R = 1 ,1291    ,313,313,313
BEGIN DESCRIPTION:
Mapping XS d65e3bb1
END DESCRIPTION:
XS GIS Cut Line= 2
      2831257.86     10211503.14      2832071.15     10210570.56
#Sta/Elev= 30
  4351.1 1274.47  4448.7 1271.91  4661.3 1261.17  4739.2 1257.76  4779.9 1256.81
  4831.2 1257.64  4838.9 1256.93  4859.7 1257.82  4888.2 1257.56  4909.1 1258.19
  4937.6  1257.7  4987.9 1258.74 5017.35 1258.13  5029.7 1258.98  5065.7 1258.78
  5107.5 1261.19  5172.1 1262.71  5207.2 1264.93  5242.3 1268.62  5249.9 1268.73
  5256.6 1269.93  5299.3 1272.51  5448.3 1279.41  5469.2 1281.02  5505.3 1282.01
  5511.9 1282.74  5526.2 1282.65  5540.4 1284.26  5554.7 1283.76  5588.5 1285.27
#Mann= 3 , 0 , 0
  4351.1     .05       0  4987.9     .05       0  5029.7     .05       0
#XS Ineff= 2 , 0
         4983.93 1261.03
Permanent Ineff=
       F       F
Bank Sta=4987.9,5029.7
XS Rating Curve= 0 ,0
Exp/Cntr=0.5,0.3

Type RM Length L Ch R = 1 ,978     ,415,415,415
BEGIN DESCRIPTION:
LITTLE LLANO 025 2.0
END DESCRIPTION:
XS GIS Cut Line= 3
      2831405.65     10211503.14      2831677.25       10211318.
      2831955.66     10211003.14
#Sta/Elev= 30
  4671.3 1274.27  4707.7 1272.02  4750.6 1268.48  4756.7 1268.48  4765.6 1267.37
  4801.5 1264.66    4865 1260.58  4888.2 1259.81  4909.2 1257.92  4987.1 1254.16
  4993.9 1253.33  4994.2 1252.83  4997.7 1252.83  4997.9 1253.33  5009.2 1253.53
  5016.7 1254.57  5101.2 1254.55  5108.7 1255.09  5115.4 1254.66  5137.2 1255.53
  5143.9 1254.71  5186.7 1254.27  5221.7 1254.37  5264.3 1255.39  5339.1 1259.16
  5363.9 1261.29  5370.6 1261.19  5378.1 1261.96    5399 1262.64  5420.3 1264.71
#Mann= 5 ,-1 , 0
  4671.3     .05       0  4993.9     .05       0  4997.9     .05       0
  5186.7     .12       0  5339.1     .05       0
Bank Sta=4993.9,4997.9
XS Rating Curve= 0 ,0
Exp/Cntr=0.3,0.1

Type RM Length L Ch R = 1 ,563     ,182,182,182
BEGIN DESCRIPTION:
Mapping XS 2f204b9b
END DESCRIPTION:
XS GIS Cut Line= 3
      2831609.72     10211860.19        2832101.     10211474.09
      2832254.59     10211310.82
#Sta/Elev= 30
  4593.7 1263.98    4596 1263.04  4645.7 1261.09  4660.2 1260.09  4666.5 1260.35
  4674.6 1259.64  4695.4 1259.12  4709.9 1258.01  4730.7 1257.81  4788.5 1254.54
  4802.9 1254.42  4830.2  1252.6  4887.9 1250.79  4902.4 1250.86  4952.1 1248.81
  5059.2 1249.25  5072.3 1248.77  5148.9 1248.56  5149.2 1248.06  5152.7 1248.06
  5152.9 1248.56  5170.6 1248.78  5264.9 1249.15  5308.7 1251.67  5335.7 1252.86
    5343 1253.76  5349.9  1253.6  5378.2 1255.18  5399.2 1256.98  5442.7 1258.96
#Mann= 5 ,-1 , 0
  4593.7     .05       0  5148.9     .03       0  5152.9     .05       0
  5170.6     .12       0  5308.7     .05       0
Bank Sta=5148.9,5152.9
XS Rating Curve= 0 ,0
Exp/Cntr=0.3,0.1

Type RM Length L Ch R = 1 ,381     ,212,212,212
BEGIN DESCRIPTION:
Mapping XS 527d48dc
END DESCRIPTION:
XS GIS Cut Line= 3
      2831757.81     10212015.18      2832249.08     10211552.97
      2832344.55     10211400.76
#Sta/Elev= 30
  4630.2 1262.11  4729.2 1255.46  4764.6 1254.65  4778.5 1252.93  4828.3 1250.37
    4906 1248.12  4955.8 1246.14  5017.3 1245.45  5017.5 1244.95    5021 1244.95
  5021.3 1245.45  5054.5 1246.15  5082.8 1245.76  5171.2 1246.39  5224.4 1247.12
  5273.8 1247.12  5295.2 1247.79  5304.7 1248.33  5309.1 1249.19  5318.3 1249.28
  5360.9 1251.83  5382.2 1253.93  5403.4  1255.3  5418.7 1257.19    5434  1258.2
  5439.9 1257.99  5446.2 1259.12  5455.2 1259.64  5461.1 1259.26  5484.4 1260.47
#Mann= 5 ,-1 , 0
  4630.2     .05       0  5017.3     .05       0  5021.3     .05       0
  5171.2     .12       0  5318.3     .05       0
Bank Sta=5017.3,5021.3
XS Rating Curve= 0 ,0
Exp/Cntr=0.3,0.1

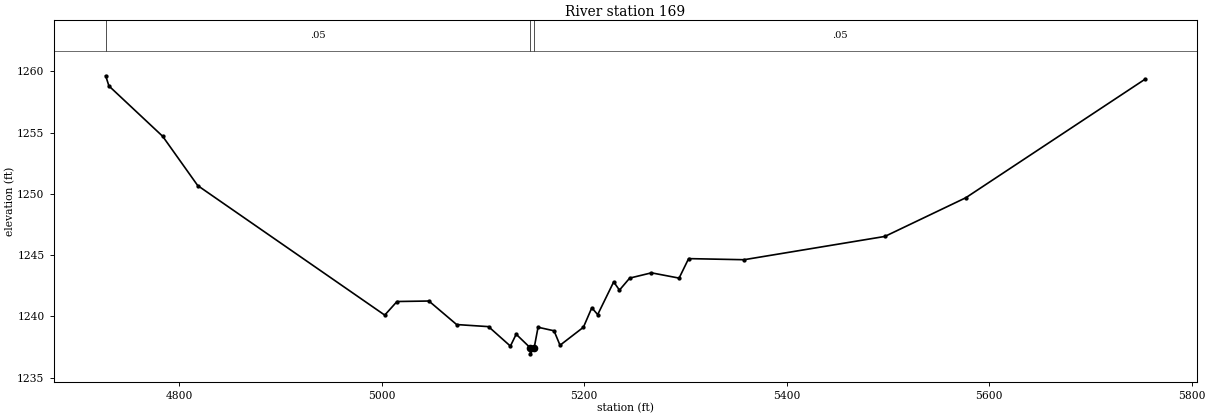
Type RM Length L Ch R = 1 ,169     ,0,0,0
BEGIN DESCRIPTION:
LITTLE LLANO 025 1.0
END DESCRIPTION:
XS GIS Cut Line= 3
      2831916.92     10212069.17      2832459.43      10211756.4
      2832452.53     10211356.57
#Sta/Elev= 30
  4727.5 1259.64  4730.7 1258.81  4783.8  1254.7  4818.4 1250.68  5003.1 1240.11
  5015.2 1241.22  5046.7 1241.26  5074.1 1239.34  5105.6 1239.17  5127.2 1237.58
  5132.9 1238.55  5146.7 1237.45    5147 1236.95  5150.7 1237.45  5154.5 1239.12
  5170.3 1238.83  5176.2 1237.65  5199.3 1239.12  5207.6 1240.71  5213.4 1240.15
  5229.2 1242.82  5234.9 1242.15    5245 1243.13  5266.5 1243.56  5293.8 1243.13
  5303.2 1244.72  5357.9 1244.63    5497 1246.53    5577 1249.69  5753.6 1259.34
#Mann= 3 ,-1 , 0
  4727.5     .05       0  5146.7     .05       0  5150.7     .05       0
Bank Sta=5146.7,5150.7
XS Rating Curve= 0 ,0
Exp/Cntr=0.3,0.1

Chan Stop Cuts=-1
Use User Specified Reach Order=0
Composite Channel Slope=5