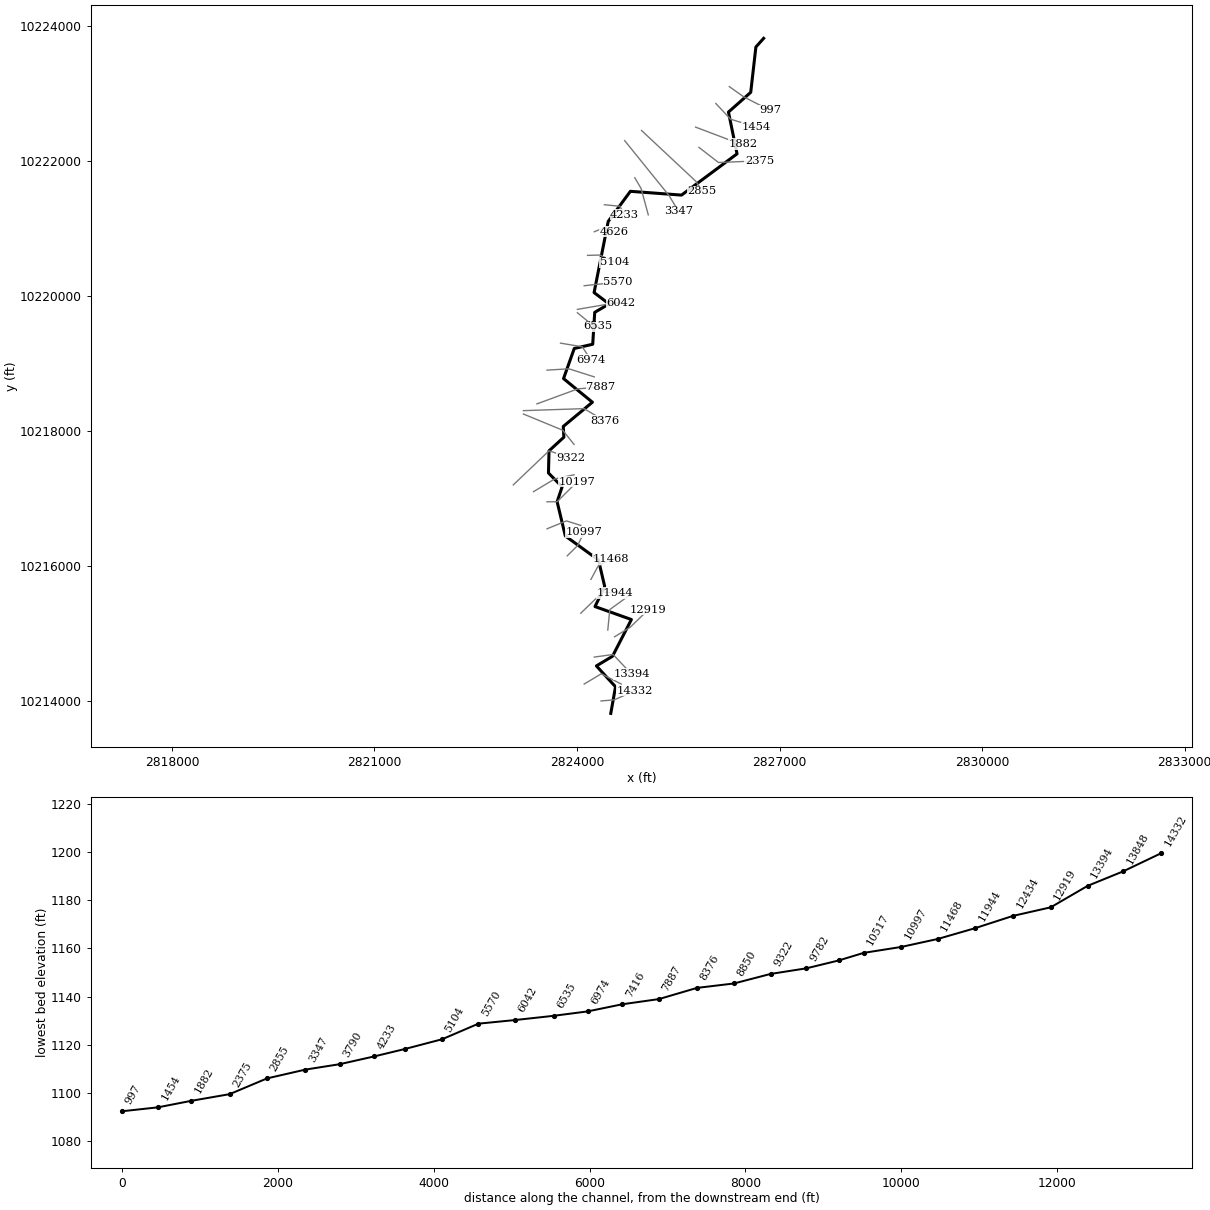
--- LITTLE LLANO 026.prj (project) ---

Proj Title=LITTLE LLANO 026 Base Level Engineering
Current Plan=p01
Default Exp/Contr=0.3,0.1
English Units
Geom File=g01
Flow File=f01
Plan File=p01
BEGIN DESCRIPTION:
LITTLE LLANO 026
END DESCRIPTION:

--- LITTLE LLANO 026.p01 (plan) ---

Plan Title=Multiple Run
Short Identifier=Multiple
Geom File=g01
Flow File=f01
Subcritical Flow
K Sum by GR= 0
Std Step Tol= 0.01
Critical Tol= 0.01
Num of Std Step Trials= 20
Max Error Tol= 0.3
Flow Tol Ratio= 0.001
Split Flow NTrial= 30
Split Flow Tol= 0.02
Split Flow Ratio= 0.02
Log Output Level= 0
Friction Slope Method= 1
Unsteady Friction Slope Method= 2
Unsteady Bridges Friction Slope Method= 1
Parabolic Critical Depth
Global Vel Dist=  1 , 1 , 1
Global Log Level= 0
CheckData=True
Encroach Param= -1, 0, 0, 0
BEGIN DESCRIPTION:
Multiple Run
END DESCRIPTION:

--- LITTLE LLANO 026.f01 (steady flow) ---

Flow Title=Multiple
Number of Profiles=7
Profile Names=10-year,25-year,50-year,1pct_min,100-year,1pct_plu,500-year
River Rch & RM= LITTLE LLANO 026,Reach-1,14332
     490     803     994     706    1321    2474    1809
River Rch & RM= LITTLE LLANO 026,Reach-1,3790
     669    1119    1403     971    1885    3659    2575
Boundary for River Rch & Prof#=LITTLE LLANO 026,Reach-1,1
Up Type=0
Dn Type=3
Dn Slope=0.005
Boundary for River Rch & Prof#=LITTLE LLANO 026,Reach-1,2
Up Type=0
Dn Type=3
Dn Slope=0.005
Boundary for River Rch & Prof#=LITTLE LLANO 026,Reach-1,3
Up Type=0
Dn Type=3
Dn Slope=0.005
Boundary for River Rch & Prof#=LITTLE LLANO 026,Reach-1,4
Up Type=0
Dn Type=3
Dn Slope=0.005
Boundary for River Rch & Prof#=LITTLE LLANO 026,Reach-1,5
Up Type=0
Dn Type=3
Dn Slope=0.005
Boundary for River Rch & Prof#=LITTLE LLANO 026,Reach-1,6
Up Type=0
Dn Type=3
Dn Slope=0.005
Boundary for River Rch & Prof#=LITTLE LLANO 026,Reach-1,7
Up Type=0
Dn Type=3
Dn Slope=0.005

--- LITTLE LLANO 026.g01 (geometry) ---

Geom Title=Existing Conditions

River Reach=LITTLE LLANO 026,Reach-1
Reach XY= 30
      2824500.00     10213819.00      2824570.25     10214213.00
      2824287.00     10214522.00      2824525.50     10214665.00
      2824805.25     10215209.00      2824266.50     10215401.00
      2824410.00     10215698.00      2824318.25     10216090.00
      2823826.75     10216447.00      2823705.25     10216954.00
      2823779.25     10217174.00      2823577.00     10217380.00
      2823585.25     10217708.00      2823805.25     10217910.00
      2823796.25     10218069.00      2824227.75     10218428.00
      2823800.25     10218778.00      2823959.00     10219224.00
      2824232.50     10219287.00      2824262.00     10219759.00
      2824474.50     10219884.00      2824252.75     10220052.00
      2824462.00     10221106.00      2824790.25     10221552.00
      2825548.00     10221496.00      2826370.25     10222107.00
      2826243.25     10222726.00      2826573.00     10223018.00
      2826649.50     10223690.00      2826764.25     10223818.00

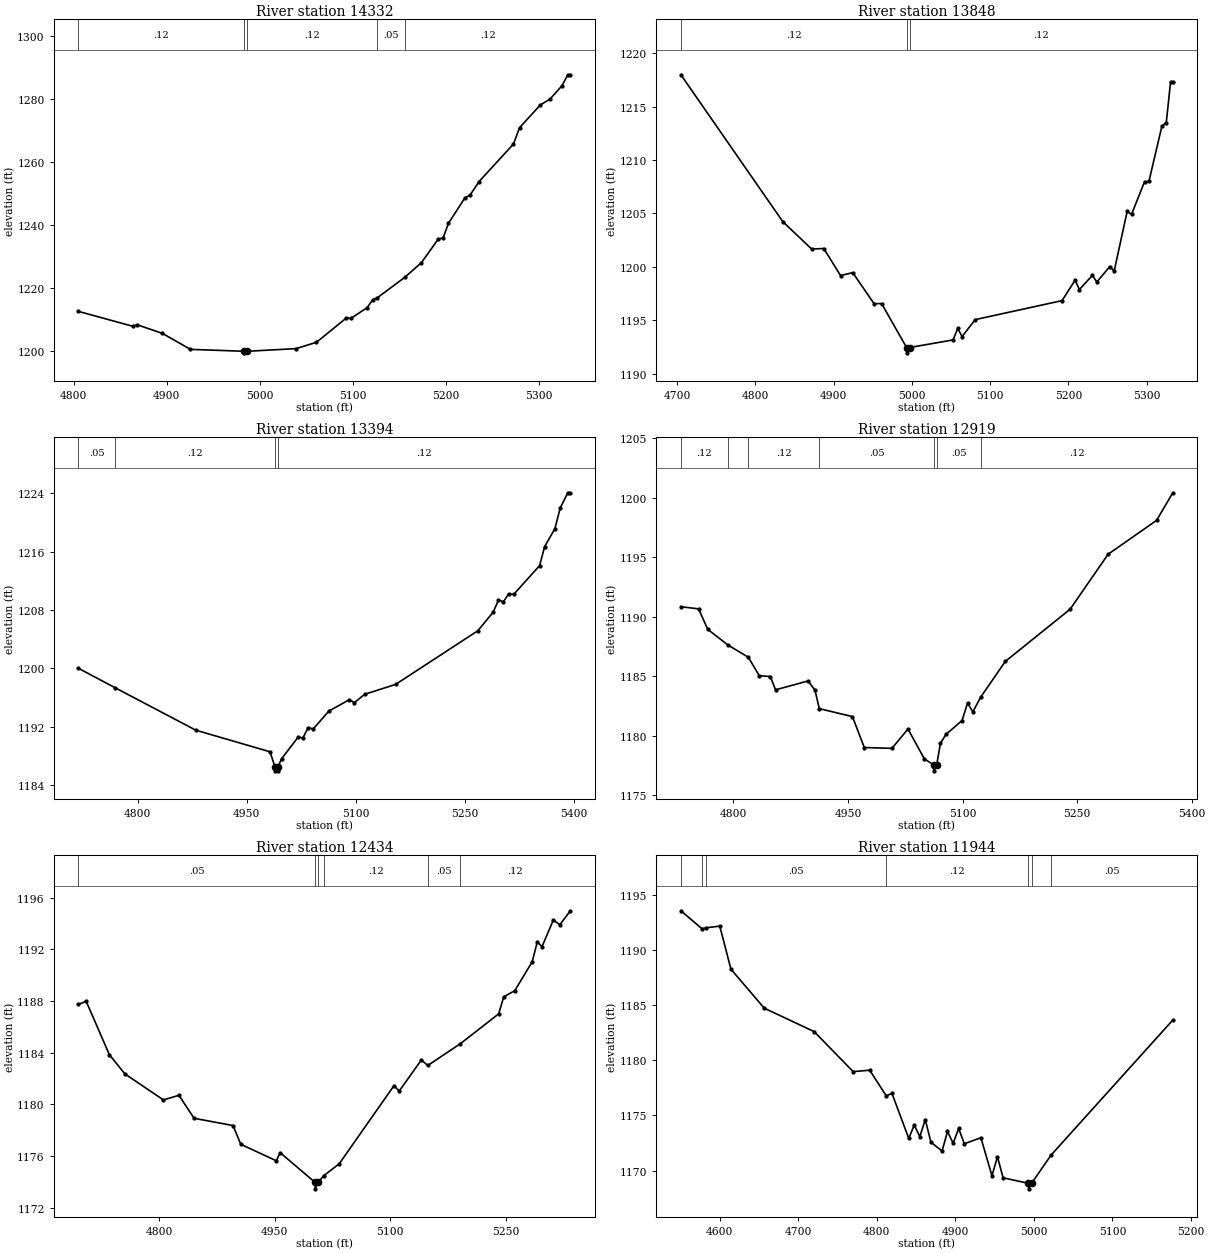
Type RM Length L Ch R = 1,14332,484,484,484
BEGIN DESCRIPTION:
LITTLE LLANO 026 31.0
END DESCRIPTION:
XS GIS Cut Line= 3
      2824355.70     10214003.11      2824549.75     10214019.00
      2824855.65     10214153.10
#Sta/Elev= 30
  4805.3 1212.56  4863.5 1207.85  4868.5 1208.31  4895.6 1205.57  4925.7 1200.51
  4983.0 1199.91  4983.2 1199.41  4987.0 1199.91  5039.2 1200.75  5061.1 1202.75
  5092.9 1210.38  5098.4 1210.39  5115.7 1213.76  5121.7 1216.32  5126.0 1216.76
  5156.1 1223.37  5173.9 1228.00  5191.8 1235.40  5197.3 1235.94  5203.0 1240.50
  5220.7 1248.59  5226.1 1249.38  5235.8 1253.71  5272.9 1265.66  5279.4 1270.83
  5301.7 1278.02  5312.2 1279.93  5325.1 1284.17  5331.3 1287.62  5334.0 1287.62
#Mann=5,-1,0
  4805.3    0.12       0  4983.0    0.07       0  4987.0    0.12       0
  5126.0    0.05       0  5156.1    0.12       0
Bank Sta=4983,4987
Exp/Cntr=0.3,0.1

Type RM Length L Ch R = 1,13848,454,454,454
BEGIN DESCRIPTION:
LITTLE LLANO 026 30.0
END DESCRIPTION:
XS GIS Cut Line= 3
      2824105.73     10214253.14      2824358.75     10214405.00
      2824655.66     10214253.12
#Sta/Elev= 30
  4704.9 1217.98  4835.1 1204.23  4872.0 1201.66  4887.5 1201.71  4908.9 1199.18
  4924.5 1199.45  4951.7 1196.55  4961.4 1196.55  4993.3 1192.44  4993.5 1191.94
  4997.3 1192.44  5052.7 1193.15  5058.7 1194.22  5064.3 1193.46  5080.9 1195.05
  5192.0 1196.83  5208.6 1198.74  5214.2 1197.87  5230.8 1199.20  5236.4 1198.57
  5253.0 1200.02  5258.6 1199.60  5275.2 1205.18  5280.8 1204.91  5297.4 1207.96
  5303.0 1207.99  5319.6 1213.17  5325.2 1213.51  5330.7 1217.31  5333.5 1217.31
#Mann=3,-1,0
  4704.9    0.12       0  4993.3    0.07       0  4997.3    0.12       0
Bank Sta=4993.3,4997.3
Exp/Cntr=0.3,0.1

Type RM Length L Ch R = 1,13394,475,475,475
BEGIN DESCRIPTION:
LITTLE LLANO 026 29.0
END DESCRIPTION:
XS GIS Cut Line= 3
      2824255.66     10214653.11      2824534.50     10214691.00
      2824805.68     10214403.11
#Sta/Elev= 30
  4718.6 1200.01  4768.6 1197.37  4880.1 1191.53  4982.3 1188.57  4989.1 1186.46
  4989.4 1185.96  4992.9 1185.96  4993.1 1186.46  4998.1 1187.61  5020.7 1190.55
  5027.5 1190.48  5034.8 1191.88  5041.7 1191.70  5063.1 1194.14  5091.5 1195.72
  5098.3 1195.30  5112.5 1196.45  5155.0 1197.80  5268.3 1205.16  5289.3 1207.70
  5296.6 1209.35  5303.5 1209.14  5310.7 1210.21  5317.6 1210.14  5353.2 1214.08
  5360.1 1216.67  5374.3 1219.16  5381.6 1221.99  5392.1 1224.06  5395.5 1224.06
#Mann=4,-1,0
  4718.6    0.05       0  4768.6    0.12       0  4989.1    0.07       0
  4993.1    0.12       0
Bank Sta=4989.1,4993.1
Exp/Cntr=0.3,0.1

Type RM Length L Ch R = 1,12919,485,485,485
BEGIN DESCRIPTION:
LITTLE LLANO 026 28.0
END DESCRIPTION:
XS GIS Cut Line= 3
      2824555.71     10214953.13      2824785.25     10215093.00
      2825055.67     10215353.10
#Sta/Elev= 30
  4731.2 1190.83  4754.4 1190.65  4766.3 1188.93  4792.8 1187.61  4819.5 1186.58
  4833.8 1185.03  4848.3 1184.96  4855.1 1183.84  4897.7 1184.59  4906.8 1183.80
  4912.4 1182.26  4955.8 1181.59  4971.3 1178.99  5007.5 1178.92  5028.5 1180.55
  5049.9 1178.04  5062.1 1177.53  5062.3 1177.03  5066.1 1177.53  5071.0 1179.34
  5078.2 1180.09  5099.3 1181.26  5106.5 1182.73  5113.4 1181.99  5123.8 1183.23
  5155.9 1186.23  5240.8 1190.62  5290.5 1195.24  5354.0 1198.09  5375.2 1200.41
#Mann=7,-1,0
  4731.2    0.12       0  4792.8    0.05       0  4819.5    0.12       0
  4912.4    0.05       0  5062.1    0.05       0  5066.1    0.05       0
  5123.8    0.12       0
Bank Sta=5062.1,5066.1
Exp/Cntr=0.3,0.1

Type RM Length L Ch R = 1,12434,490,490,490
BEGIN DESCRIPTION:
LITTLE LLANO 026 27.0
END DESCRIPTION:
XS GIS Cut Line= 3
      2824455.69     10215053.13      2824485.25     10215357.00
      2824755.72     10215553.14
#Sta/Elev= 30
  4694.7 1187.74  4704.7 1187.99  4734.9 1183.85  4755.0 1182.37  4805.2 1180.35
  4825.3 1180.71  4845.0 1178.93  4895.6 1178.37  4905.7 1176.92  4951.9 1175.64
  4956.9 1176.27  5002.3 1173.97  5002.6 1173.47  5006.3 1173.97  5013.4 1174.48
  5033.7 1175.41  5104.8 1181.45  5111.7 1181.04  5140.4 1183.44  5148.9 1183.02
  5191.3 1184.71  5240.9 1187.01  5247.6 1188.34  5261.8 1188.80  5284.6 1191.05
  5291.1 1192.58  5297.3 1192.22  5312.0 1194.27  5320.5 1193.91  5334.1 1194.99
#Mann=6,-1,0
  4694.7    0.05       0  5002.3    0.05       0  5006.3    0.05       0
  5013.4    0.12       0  5148.9    0.05       0  5191.3    0.12       0
Bank Sta=5002.3,5006.3
Exp/Cntr=0.3,0.1

Type RM Length L Ch R = 1,11944,476,476,476
BEGIN DESCRIPTION:
LITTLE LLANO 026 26.0
END DESCRIPTION:
XS GIS Cut Line= 3
      2824055.69     10215303.12      2824379.25     10215615.00
      2824555.65     10215603.11
#Sta/Elev= 30
  4550.6 1193.58  4577.6 1191.94  4582.4 1192.03  4600.1 1192.19  4614.3 1188.28
  4656.7 1184.74  4720.3 1182.61  4769.9 1178.98  4791.0 1179.11  4812.0 1176.78
  4819.3 1177.01  4840.7 1172.91  4847.6 1174.13  4854.8 1173.08  4861.7 1174.63
  4868.9 1172.57  4883.1 1171.77  4890.0 1173.55  4897.2 1172.47  4904.2 1173.82
  4911.4 1172.43  4932.5 1172.98  4946.6 1169.53  4953.6 1171.25  4960.8 1169.34
  4993.0 1168.84  4993.3 1168.34  4997.0 1168.84  5021.8 1171.40  5176.8 1183.66
#Mann=7,-1,0
  4550.6    0.05       0  4577.6    0.12       0  4582.4    0.05       0
  4812.0    0.12       0  4993.0    0.07       0  4997.0    0.12       0
  5021.8    0.05       0
Bank Sta=4993,4997
Exp/Cntr=0.3,0.1

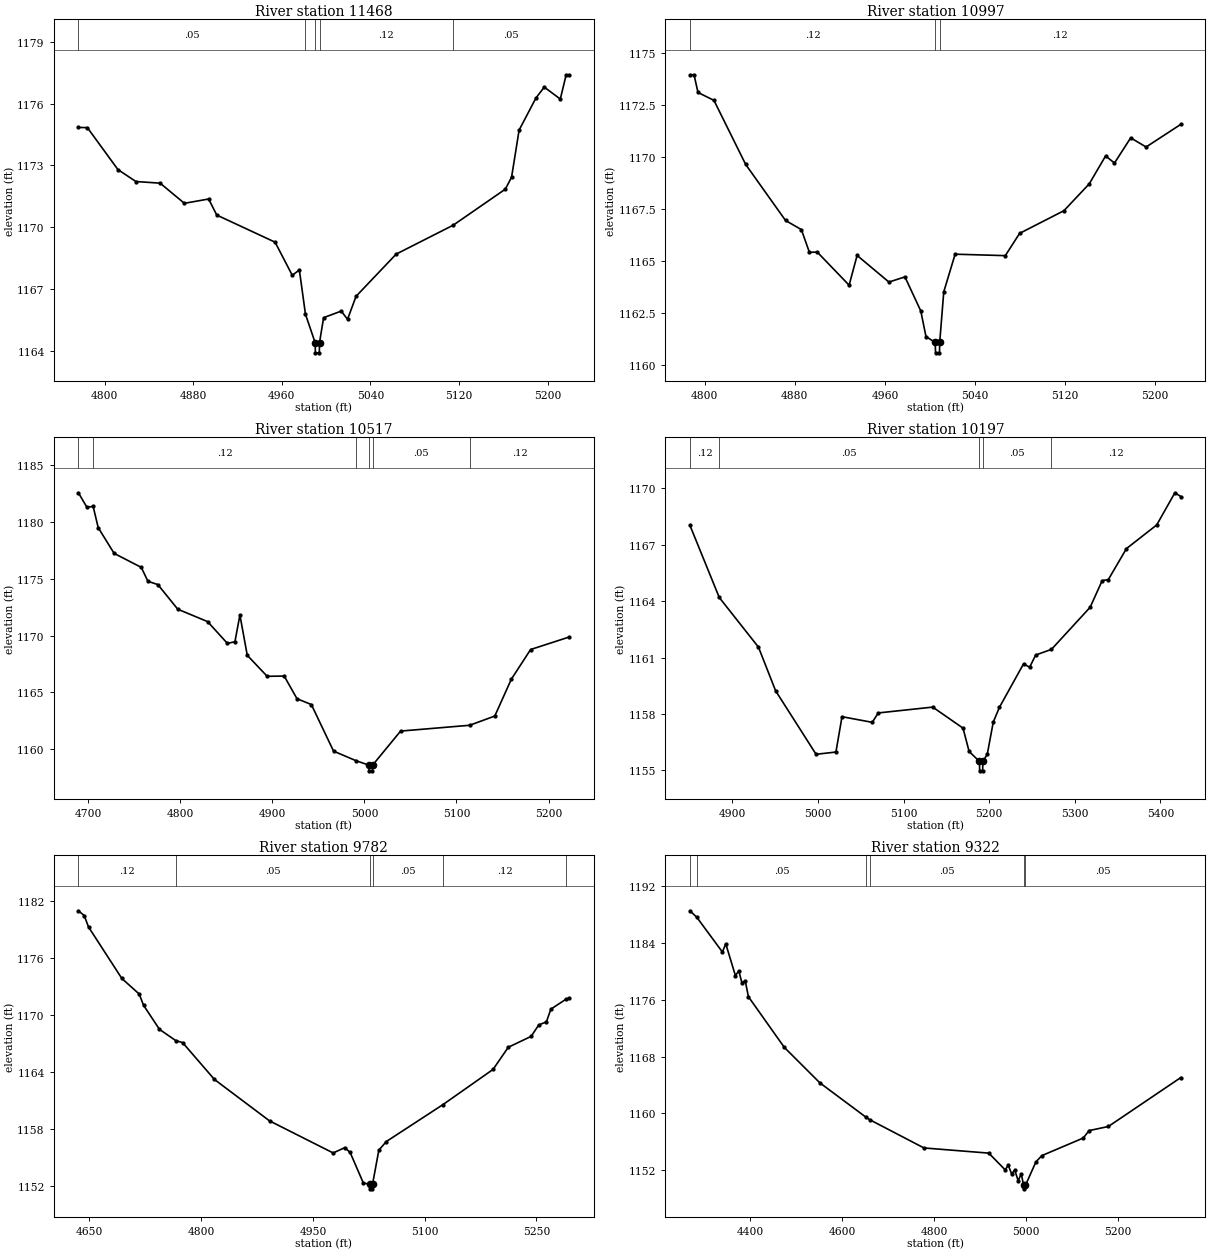
Type RM Length L Ch R = 1,11468,471,471,471
BEGIN DESCRIPTION:
LITTLE LLANO 026 25.0
END DESCRIPTION:
XS GIS Cut Line= 3
      2824205.70     10215803.15      2824311.75     10216000.00
      2824505.65     10216103.09
#Sta/Elev= 30
  4776.4 1174.85  4784.5 1174.84  4812.1 1172.80  4828.3 1172.22  4850.2 1172.14
  4872.1 1171.16  4894.0 1171.37  4901.3 1170.59  4954.0 1169.27  4969.5 1167.66
  4975.9 1167.92  4981.4 1165.77  4990.1 1164.39  4990.4 1163.89  4993.9 1163.89
  4994.1 1164.39  4997.8 1165.60  5013.7 1165.92  5019.4 1165.52  5027.1 1166.64
  5063.3 1168.69  5114.9 1170.10  5161.9 1171.85  5167.5 1172.43  5174.3 1174.72
  5189.5 1176.28  5197.0 1176.81  5211.5 1176.23  5216.8 1177.41  5219.6 1177.41
#Mann=5,-1,0
  4776.4    0.05       0  4981.4    0.12       0  4990.1    0.07       0
  4994.1    0.12       0  5114.9    0.05       0
Bank Sta=4990.1,4994.1
Exp/Cntr=0.3,0.1

Type RM Length L Ch R = 1,10997,480,480,480
BEGIN DESCRIPTION:
LITTLE LLANO 026 24.0
END DESCRIPTION:
XS GIS Cut Line= 3
      2823855.66     10216153.09      2824007.25     10216303.00
      2824105.68     10216503.10
#Sta/Elev= 30
  4786.8 1173.93  4790.4 1173.93  4793.9 1173.08  4808.1 1172.70  4836.3 1169.62
  4871.7 1166.93  4885.8 1166.49  4892.9 1165.40  4899.9 1165.41  4928.2 1163.82
  4935.3 1165.25  4963.6 1163.97  4977.8 1164.22  4991.9 1162.58  4996.5 1161.35
  5004.7 1161.07  5005.0 1160.57  5008.5 1160.57  5008.7 1161.07  5012.3 1163.50
  5022.4 1165.31  5067.0 1165.24  5079.7 1166.31  5119.1 1167.40  5141.6 1168.69
  5156.1 1170.03  5164.0 1169.69  5178.4 1170.90  5192.1 1170.46  5223.0 1171.55
#Mann=3,-1,0
  4786.8    0.12       0  5004.7    0.07       0  5008.7    0.12       0
Bank Sta=5004.7,5008.7
Exp/Cntr=0.3,0.1

Type RM Length L Ch R = 1,10517,320,320,320
BEGIN DESCRIPTION:
LITTLE LLANO 026 23.0
END DESCRIPTION:
XS GIS Cut Line= 3
      2823555.73     10216553.13      2823843.50     10216670.00
      2824055.71     10216603.10
#Sta/Elev= 30
  4689.4 1182.53  4698.7 1181.25  4705.4 1181.34  4710.9 1179.47  4728.2 1177.21
  4757.7 1175.98  4764.9 1174.76  4775.7 1174.47  4797.3 1172.31  4829.7 1171.22
  4851.3 1169.30  4859.4 1169.46  4864.8 1171.80  4872.8 1168.26  4894.4 1166.42
  4912.9 1166.44  4926.8 1164.45  4942.4 1163.94  4966.5 1159.85  4990.9 1159.01
  5004.9 1158.62  5005.2 1158.12  5008.7 1158.12  5008.9 1158.62  5039.3 1161.61
  5114.3 1162.12  5141.6 1162.93  5159.6 1166.17  5180.5 1168.77  5222.5 1169.87
#Mann=6,-1,0
  4689.4    0.05       0  4705.4    0.12       0  4990.9    0.05       0
  5004.9    0.05       0  5008.9    0.05       0  5114.3    0.12       0
Bank Sta=5004.9,5008.9
Exp/Cntr=0.3,0.1

Type RM Length L Ch R = 1,10197,415,415,415
BEGIN DESCRIPTION:
LITTLE LLANO 026 22.0
END DESCRIPTION:
XS GIS Cut Line= 3
      2823555.65     10216953.11      2823705.25     10216954.00
      2824005.65     10217253.08
#Sta/Elev= 30
  4850.4 1168.03  4884.6 1164.20  4930.4 1161.56  4950.4 1159.24  4997.7 1155.86
  5020.9 1155.98  5028.0 1157.86  5063.3 1157.56  5070.4 1158.06  5134.0 1158.37
  5169.4 1157.25  5176.5 1156.01  5188.6 1155.48  5188.8 1154.98  5192.3 1154.98
  5192.6 1155.48  5197.7 1155.86  5204.7 1157.57  5211.8 1158.35  5240.1 1160.67
  5247.2 1160.49  5254.3 1161.14  5272.7 1161.44  5317.9 1163.68  5332.0 1165.10
  5339.1 1165.15  5360.3 1166.80  5395.7 1168.06  5416.9 1169.77  5423.9 1169.57
#Mann=5,-1,0
  4850.4    0.12       0  4884.6    0.05       0  5188.6    0.05       0
  5192.6    0.05       0  5272.7    0.12       0
Bank Sta=5188.6,5192.6
Exp/Cntr=0.3,0.1

Type RM Length L Ch R = 1,9782,460,460,460
BEGIN DESCRIPTION:
LITTLE LLANO 026 21.0
END DESCRIPTION:
XS GIS Cut Line= 3
      2823355.68     10217103.11      2823668.25     10217291.00
      2823955.72     10217353.12
#Sta/Elev= 30
  4635.3 1181.00  4643.1 1180.50  4648.9 1179.29  4693.6 1173.87  4716.9 1172.23
  4722.7 1171.05  4744.1 1168.51  4765.9 1167.33  4775.2 1167.11  4817.9 1163.23
  4891.8 1158.87  4977.2 1155.49  4992.8 1156.05  5000.0 1155.54  5017.8 1152.31
  5026.1 1152.21  5026.3 1151.71  5029.8 1151.71  5030.1 1152.21  5038.5 1155.78
  5048.5 1156.69  5124.7 1160.59  5191.8 1164.29  5212.2 1166.62  5242.9 1167.77
  5253.1 1168.97  5263.4 1169.30  5269.4 1170.64  5290.2 1171.71  5294.1 1171.79
#Mann=6,-1,0
  4635.3    0.12       0  4765.9    0.05       0  5026.1    0.05       0
  5030.1    0.05       0  5124.7    0.12       0  5290.2    0.05       0
Bank Sta=5026.1,5030.1
Exp/Cntr=0.3,0.1

Type RM Length L Ch R = 1,9322,472,472,472
BEGIN DESCRIPTION:
LITTLE LLANO 026 20.0
END DESCRIPTION:
XS GIS Cut Line= 3
      2823055.67     10217203.10      2823585.25     10217708.00
      2823905.72     10217603.10
#Sta/Elev= 30
  4268.3 1188.54  4283.3 1187.61  4338.9 1182.73  4346.2 1183.89  4367.2 1179.41
  4374.5 1180.07  4381.4 1178.40  4388.6 1178.67  4395.5 1176.44  4473.6 1169.31
  4551.2 1164.30  4652.1 1159.44  4659.5 1159.12  4777.7 1155.14  4918.9 1154.41
  4954.5 1152.06  4961.4 1152.70  4968.6 1151.50  4975.5 1152.02  4982.8 1150.54
  4989.7 1151.46  4994.8 1149.88  4995.1 1149.38  4998.8 1149.88  5021.5 1153.17
  5034.5 1154.06  5124.8 1156.54  5137.2 1157.58  5179.3 1158.16  5337.2 1165.06
#Mann=6,-1,0
  4268.3    0.12       0  4283.3    0.05       0  4652.1    0.12       0
  4659.5    0.05       0  4994.8    0.05       0  4998.8    0.05       0
Bank Sta=4994.8,4998.8
Exp/Cntr=0.3,0.1

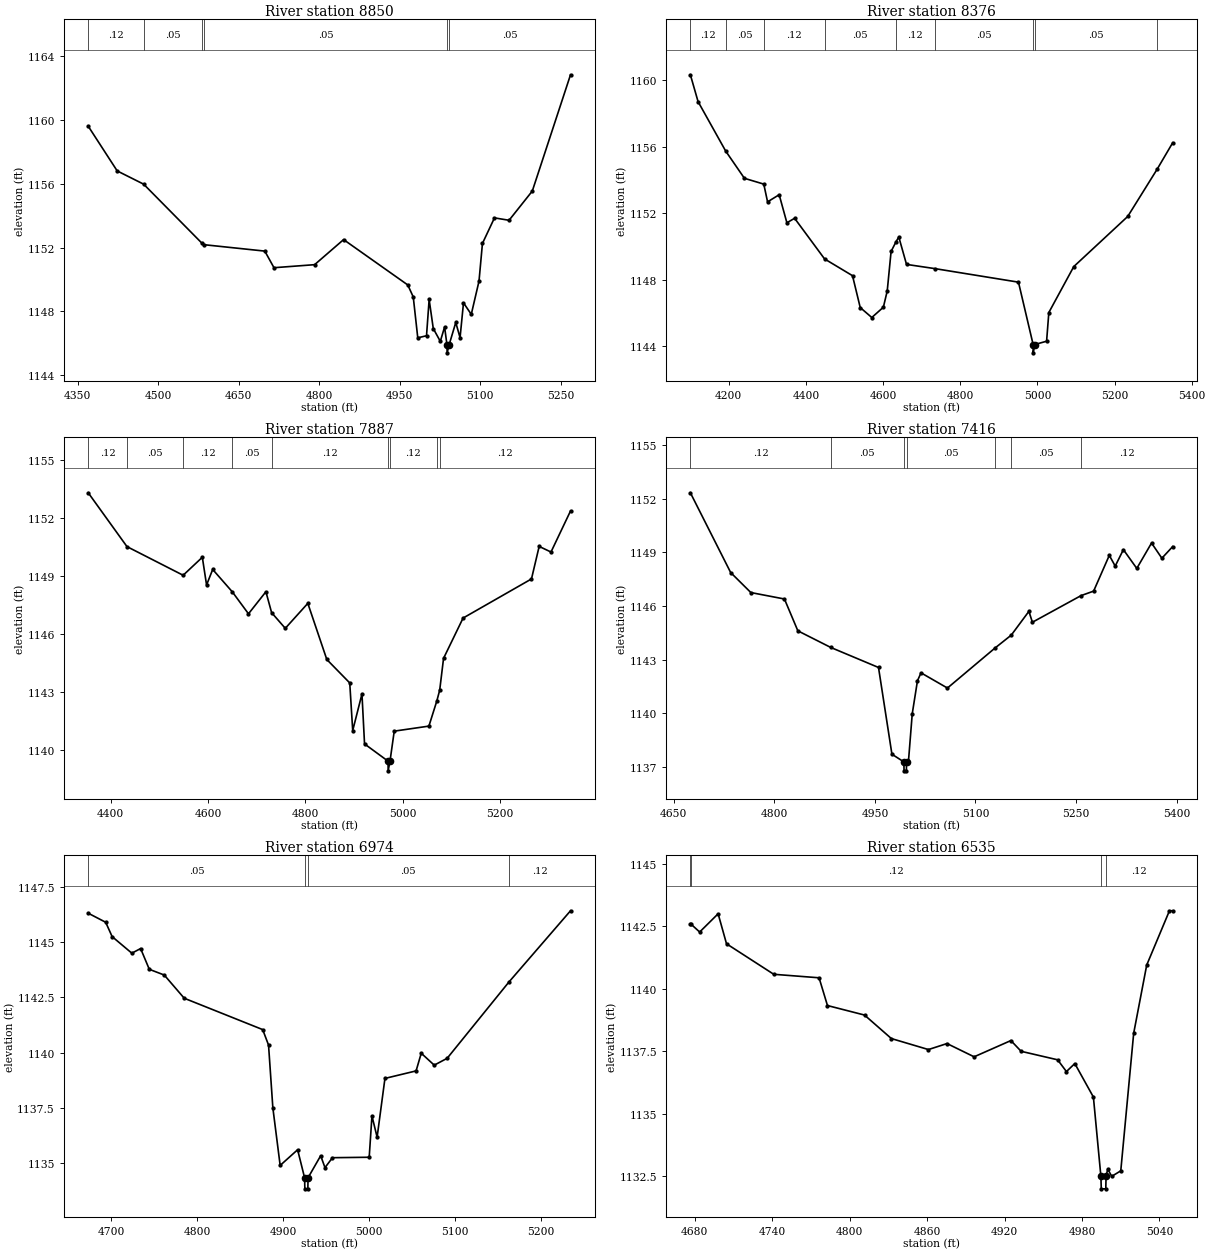
Type RM Length L Ch R = 1,8850,474,474,474
BEGIN DESCRIPTION:
LITTLE LLANO 026 19.0
END DESCRIPTION:
XS GIS Cut Line= 3
      2823205.72     10218253.10      2823788.50     10218013.00
      2823955.66     10217803.14
#Sta/Elev= 30
  4369.7 1159.60  4423.7 1156.80  4473.0 1155.97  4581.7 1152.27  4585.7 1152.18
  4698.7 1151.78  4715.8 1150.74  4791.5 1150.93  4845.5 1152.50  4965.1 1149.66
  4975.3 1148.91  4983.7 1146.35  5000.0 1146.48  5004.9 1148.75  5012.6 1146.93
  5025.7 1146.13  5033.7 1147.03  5038.1 1145.91  5038.4 1145.41  5042.1 1145.91
  5054.5 1147.31  5062.5 1146.36  5068.9 1148.54  5083.4 1147.82  5097.8 1149.90
  5104.2 1152.26  5126.6 1153.86  5153.8 1153.71  5197.1 1155.54  5268.3 1162.82
#Mann=6,-1,0
  4369.7    0.12       0  4473.0    0.05       0  4581.7    0.12       0
  4585.7    0.05       0  5038.1    0.05       0  5042.1    0.05       0
Bank Sta=5038.1,5042.1
Exp/Cntr=0.3,0.1

Type RM Length L Ch R = 1,8376,489,489,489
BEGIN DESCRIPTION:
LITTLE LLANO 026 18.0
END DESCRIPTION:
XS GIS Cut Line= 3
      2823205.65     10218303.11      2824104.75     10218333.00
      2824405.68     10218153.11
#Sta/Elev= 30
  4100.4 1160.34  4120.4 1158.72  4192.0 1155.74  4240.5 1154.10  4290.7 1153.75
  4300.5 1152.68  4330.6 1153.11  4350.6 1151.42  4370.6 1151.69  4448.3 1149.24
  4520.7 1148.23  4540.7 1146.31  4570.7 1145.71  4600.7 1146.33  4610.7 1147.31
  4620.7 1149.69  4633.8 1150.29  4640.7 1150.56  4660.7 1148.91  4733.3 1148.66
  4950.9 1147.84  4988.9 1144.08  4989.2 1143.58  4992.9 1144.08  5023.8 1144.28
  5029.6 1146.01  5094.3 1148.78  5234.1 1151.80  5310.4 1154.65  5350.6 1156.24
#Mann=9,-1,0
  4100.4    0.12       0  4192.0    0.05       0  4290.7    0.12       0
  4448.3    0.05       0  4633.8    0.12       0  4733.3    0.05       0
  4988.9    0.05       0  4992.9    0.05       0  5310.4    0.12       0
Bank Sta=4988.9,4992.9
Exp/Cntr=0.3,0.1

Type RM Length L Ch R = 1,7887,471,471,471
BEGIN DESCRIPTION:
LITTLE LLANO 026 17.0
END DESCRIPTION:
XS GIS Cut Line= 3
      2823405.70     10218403.12      2824012.25     10218626.00
      2824355.68     10218653.11
#Sta/Elev= 30
  4353.8 1153.29  4433.4 1150.51  4548.8 1149.03  4588.2 1149.96  4596.9 1148.53
  4609.5 1149.33  4649.9 1148.17  4683.0 1147.04  4718.8 1148.18  4730.5 1147.10
  4758.6 1146.29  4804.9 1147.58  4843.9 1144.68  4891.0 1143.47  4897.1 1141.01
  4916.1 1142.90  4921.4 1140.32  4969.7 1139.43  4969.9 1138.93  4973.7 1139.43
  4982.4 1140.98  5053.6 1141.24  5069.9 1142.54  5075.8 1143.10  5083.7 1144.74
  5123.8 1146.82  5264.3 1148.84  5280.1 1150.52  5304.4 1150.23  5344.5 1152.35
#Mann=9,-1,0
  4353.8    0.12       0  4433.4    0.05       0  4548.8    0.12       0
  4649.9    0.05       0  4730.5    0.12       0  4969.7    0.07       0
  4973.7    0.12       0  5069.9    0.05       0  5075.8    0.12       0
Bank Sta=4969.7,4973.7
Exp/Cntr=0.3,0.1

Type RM Length L Ch R = 1,7416,442,442,442
BEGIN DESCRIPTION:
LITTLE LLANO 026 16.0
END DESCRIPTION:
XS GIS Cut Line= 3
      2823555.66     10218903.11      2823880.25     10218923.00
      2824255.67     10218803.12
#Sta/Elev= 30
  4674.8 1152.33  4734.9 1147.87  4765.0 1146.75  4815.1 1146.39  4835.1 1144.61
  4884.2 1143.68  4955.4 1142.56  4975.4 1137.71  4993.2 1137.28  4993.5 1136.78
  4997.0 1136.78  4997.2 1137.28  5000.0 1137.28  5005.7 1139.97  5013.5 1141.82
  5018.8 1142.26  5058.2 1141.41  5128.9 1143.64  5153.4 1144.37  5179.7 1145.70
  5184.9 1145.09  5257.5 1146.58  5276.2 1146.83  5299.6 1148.83  5308.4 1148.23
  5320.6 1149.15  5340.6 1148.10  5362.6 1149.52  5378.0 1148.67  5394.1 1149.32
#Mann=7,-1,0
  4674.8    0.12       0  4884.2    0.05       0  4993.2    0.05       0
  4997.2    0.05       0  5128.9    0.12       0  5153.4    0.05       0
  5257.5    0.12       0
Bank Sta=4993.2,4997.2
Exp/Cntr=0.3,0.1

Type RM Length L Ch R = 1,6974,439,439,439
BEGIN DESCRIPTION:
LITTLE LLANO 026 15.0
END DESCRIPTION:
XS GIS Cut Line= 3
      2823755.66     10219303.11      2824077.75     10219249.00
      2824205.70     10219053.08
#Sta/Elev= 30
  4673.4 1146.31  4693.7 1145.90  4701.2 1145.25  4724.1 1144.50  4734.3 1144.71
  4744.4 1143.77  4761.8 1143.51  4785.0 1142.46  4876.2 1141.04  4883.0 1140.34
  4888.0 1137.50  4896.5 1134.89  4916.8 1135.60  4924.9 1134.33  4925.2 1133.83
  4928.7 1133.83  4928.9 1134.33  4943.6 1135.33  4948.6 1134.79  4957.3 1135.24
  5000.0 1135.26  5003.2 1137.13  5009.2 1136.17  5018.3 1138.83  5054.5 1139.17
  5060.5 1139.97  5075.6 1139.43  5090.6 1139.74  5162.1 1143.18  5234.0 1146.42
#Mann=4,-1,0
  4673.4    0.05       0  4924.9    0.05       0  4928.9    0.05       0
  5162.1    0.12       0
Bank Sta=4924.9,4928.9
Exp/Cntr=0.3,0.1

Type RM Length L Ch R = 1,6535,493,493,493
BEGIN DESCRIPTION:
LITTLE LLANO 026 14.0
END DESCRIPTION:
XS GIS Cut Line= 3
      2824005.70     10219753.10      2824255.75     10219548.00
      2824305.69     10219553.11
#Sta/Elev= 30
  4676.6 1142.58  4677.0 1142.58  4683.8 1142.26  4698.1 1142.99  4704.6 1141.79
  4741.2 1140.57  4776.3 1140.43  4782.8 1139.32  4811.5 1138.94  4832.3 1138.00
  4861.0 1137.56  4875.4 1137.80  4896.4 1137.27  4924.9 1137.92  4932.8 1137.49
  4961.1 1137.15  4967.9 1136.68  4974.4 1137.00  4988.8 1135.66  4994.6 1132.49
  4994.9 1131.99  4998.4 1131.99  4998.6 1132.49  4999.9 1132.78  5003.0 1132.49
  5010.0 1132.71  5020.0 1138.21  5030.1 1140.94  5047.7 1143.11  5050.2 1143.11
#Mann=4,-1,0
  4676.6    0.05       0  4677.0    0.12       0  4994.6    0.07       0
  4998.6    0.12       0
Bank Sta=4994.6,4998.6
Exp/Cntr=0.3,0.1

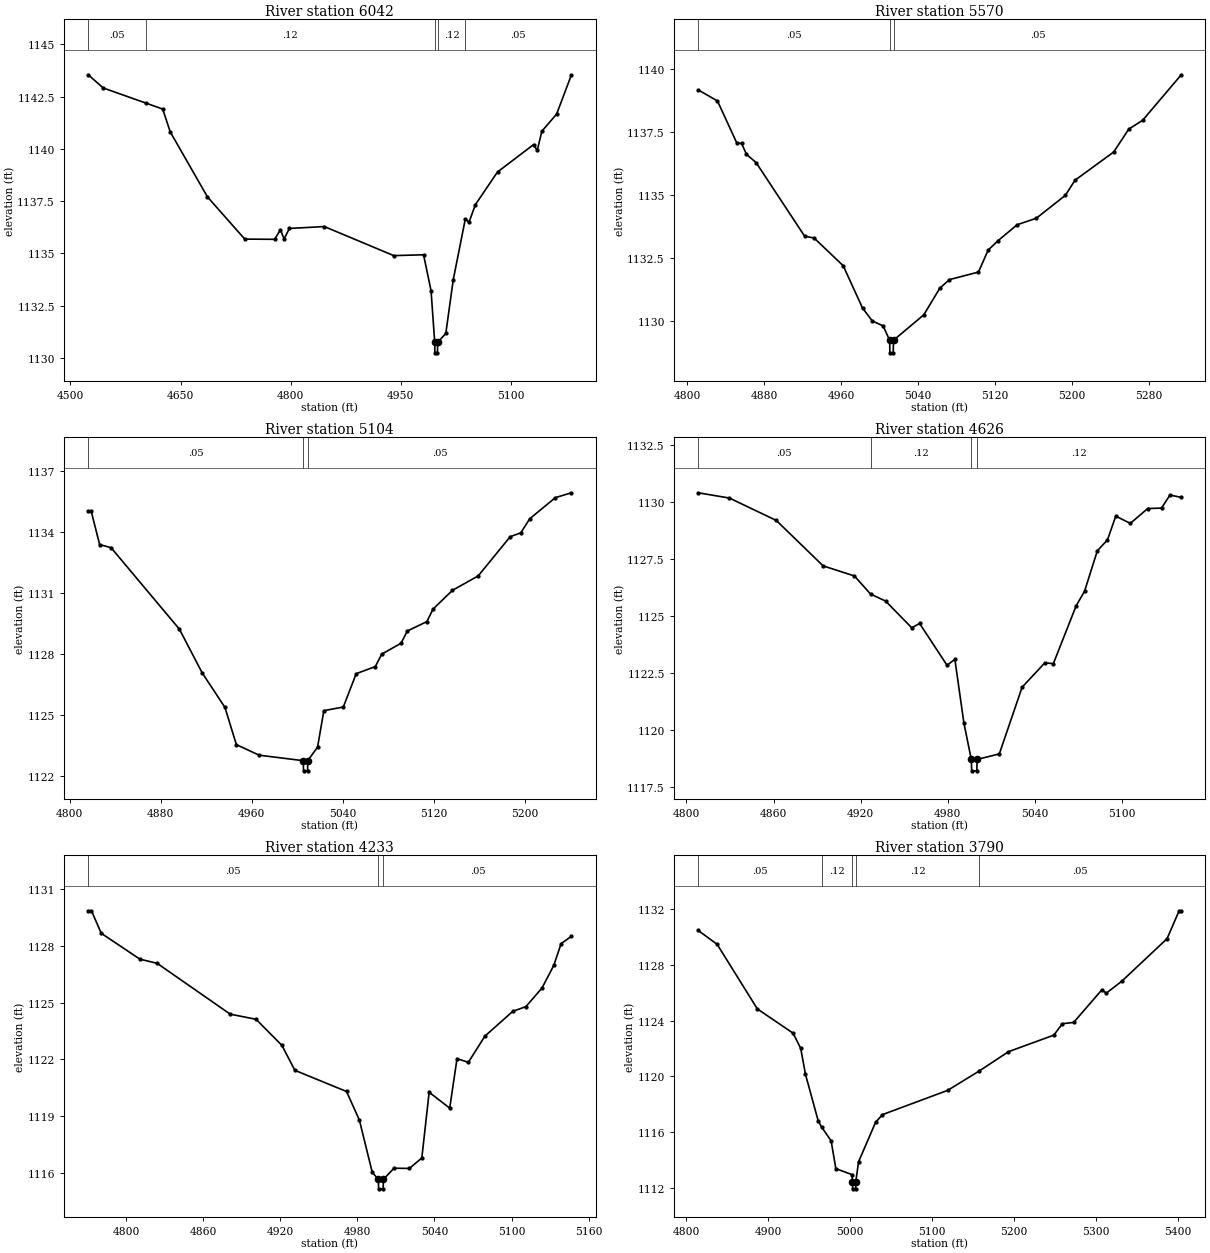
Type RM Length L Ch R = 1,6042,472,472,472
BEGIN DESCRIPTION:
LITTLE LLANO 026 13.0
END DESCRIPTION:
XS GIS Cut Line= 3
      2824005.73     10219803.12      2824474.50     10219884.00
      2824655.69     10219903.11
#Sta/Elev= 30
  4524.3 1143.54  4544.6 1142.91  4602.5 1142.19  4625.7 1141.90  4635.9 1140.81
  4686.6 1137.70  4737.4 1135.68  4778.0 1135.67  4786.0 1136.12  4791.0 1135.69
  4798.2 1136.19  4845.8 1136.28  4940.3 1134.89  4980.9 1134.93  4991.1 1133.21
  4996.1 1130.74  4996.3 1130.24  4999.8 1130.24  5000.1 1130.74  5011.2 1131.17
  5021.3 1133.73  5037.8 1136.65  5042.8 1136.49  5051.5 1137.33  5081.6 1138.89
  5130.7 1140.20  5135.7 1139.92  5142.0 1140.84  5162.1 1141.66  5182.2 1143.53
#Mann=5,-1,0
  4524.3    0.05       0  4602.5    0.12       0  4996.1    0.07       0
  5000.1    0.12       0  5037.8    0.05       0
Bank Sta=4996.1,5000.1
Exp/Cntr=0.3,0.1

Type RM Length L Ch R = 1,5570,466,466,466
BEGIN DESCRIPTION:
LITTLE LLANO 026 12.0
END DESCRIPTION:
XS GIS Cut Line= 3
      2824105.71     10220153.11      2824293.25     10220174.00
      2824605.70     10220203.11
#Sta/Elev= 30
  4811.3 1139.18  4831.4 1138.74  4851.5 1137.07  4856.5 1137.05  4861.6 1136.62
  4871.6 1136.29  4922.0 1133.37  4932.0 1133.29  4962.2 1132.19  4982.3 1130.51
  4992.4 1130.00  5003.7 1129.80  5010.5 1129.23  5010.7 1128.73  5014.2 1128.73
  5014.5 1129.23  5046.0 1130.24  5062.7 1131.30  5072.7 1131.64  5102.9 1131.94
  5112.9 1132.81  5123.0 1133.18  5143.1 1133.82  5163.1 1134.08  5193.3 1134.99
  5203.3 1135.59  5243.5 1136.71  5259.2 1137.62  5273.6 1137.97  5313.8 1139.78
#Mann=3,-1,0
  4811.3    0.05       0  5010.5    0.05       0  5014.5    0.05       0
Bank Sta=5010.5,5014.5
Exp/Cntr=0.3,0.1

Type RM Length L Ch R = 1,5104,478,478,478
BEGIN DESCRIPTION:
LITTLE LLANO 026 11.0
END DESCRIPTION:
XS GIS Cut Line= 3
      2824155.72     10220603.11      2824339.25     10220608.00
      2824555.67     10220503.12
#Sta/Elev= 30
  4816.4 1135.06  4818.9 1135.06  4826.4 1133.40  4836.4 1133.25  4896.4 1129.24
  4916.4 1127.09  4936.4 1125.39  4946.4 1123.56  4966.4 1123.04  5005.1 1122.77
  5005.4 1122.27  5008.9 1122.27  5009.1 1122.77  5017.7 1123.44  5023.2 1125.23
  5040.3 1125.41  5051.6 1127.05  5068.4 1127.40  5074.0 1128.01  5091.0 1128.55
  5096.5 1129.15  5113.6 1129.61  5119.1 1130.23  5136.1 1131.15  5158.7 1131.86
  5186.8 1133.79  5196.1 1133.98  5203.9 1134.67  5226.4 1135.71  5240.5 1135.95
#Mann=3,-1,0
  4816.4    0.05       0  5005.1    0.05       0  5009.1    0.05       0
Bank Sta=5005.1,5009.1
Exp/Cntr=0.3,0.1

Type RM Length L Ch R = 1,4626,393,393,393
BEGIN DESCRIPTION:
LITTLE LLANO 026 10.0
END DESCRIPTION:
XS GIS Cut Line= 3
      2824255.67     10220953.11      2824434.00     10221024.00
      2824555.66     10220953.13
#Sta/Elev= 30
  4808.1 1130.39  4829.6 1130.16  4861.9 1129.18  4894.2 1127.19  4915.7 1126.75
  4926.8 1125.96  4937.2 1125.65  4955.2 1124.48  4960.6 1124.67  4979.5 1122.84
  4984.9 1123.10  4991.1 1120.32  4996.2 1118.72  4996.5 1118.22  5000.0 1118.22
  5000.2 1118.72  5015.5 1118.96  5031.2 1121.88  5046.9 1122.95  5052.7 1122.91
  5068.4 1125.44  5074.2 1126.08  5083.0 1127.85  5090.0 1128.33  5095.7 1129.37
  5105.7 1129.05  5117.7 1129.70  5127.2 1129.72  5133.0 1130.29  5140.8 1130.19
#Mann=4,-1,0
  4808.1    0.05       0  4926.8    0.12       0  4996.2    0.07       0
  5000.2    0.12       0
Bank Sta=4996.2,5000.2
Exp/Cntr=0.3,0.1

Type RM Length L Ch R = 1,4233,443,443,443
BEGIN DESCRIPTION:
LITTLE LLANO 026 9.0
END DESCRIPTION:
XS GIS Cut Line= 3
      2824405.67     10221353.11      2824634.00     10221331.00
      2824705.68     10221203.12
#Sta/Elev= 30
  4770.6 1129.86  4773.1 1129.86  4780.7 1128.67  4810.8 1127.30  4824.2 1127.08
  4881.1 1124.39  4901.2 1124.12  4921.3 1122.74  4931.4 1121.42  4971.6 1120.30
  4981.6 1118.79  4991.6 1116.03  4996.3 1115.65  4996.6 1115.15  5000.1 1115.15
  5000.3 1115.65  5008.5 1116.24  5020.5 1116.23  5030.2 1116.78  5035.9 1120.26
  5051.9 1119.42  5057.6 1122.04  5066.4 1121.84  5079.3 1123.23  5101.0 1124.54
  5111.2 1124.79  5123.7 1125.77  5132.9 1126.97  5138.6 1128.12  5146.6 1128.51
#Mann=3,-1,0
  4770.6    0.05       0  4996.3    0.05       0  5000.3    0.05       0
Bank Sta=4996.3,5000.3
Exp/Cntr=0.3,0.1

Type RM Length L Ch R = 1,3790,443,443,443
BEGIN DESCRIPTION:
LITTLE LLANO 026 8.0
END DESCRIPTION:
XS GIS Cut Line= 3
      2824855.67     10221753.14      2824949.50     10221593.00
      2825055.69     10221203.10
#Sta/Elev= 30
  4814.4 1130.48  4837.6 1129.48  4886.7 1124.84  4930.3 1123.10  4939.6 1122.01
  4945.4 1120.15  4961.0 1116.79  4965.0 1116.37  4976.7 1115.37  4982.5 1113.37
  5002.3 1112.94  5002.7 1112.42  5003.0 1111.92  5006.6 1111.92  5006.8 1112.42
  5010.2 1113.86  5031.0 1116.70  5039.4 1117.25  5118.9 1118.99  5157.7 1120.39
  5193.2 1121.77  5248.6 1122.96  5259.0 1123.78  5272.7 1123.87  5307.3 1126.22
  5312.5 1125.97  5331.5 1126.83  5386.8 1129.89  5401.5 1131.89  5404.1 1131.89
#Mann=5,-1,0
  4814.4    0.05       0  4965.0    0.12       0  5002.7    0.07       0
  5006.8    0.12       0  5157.7    0.05       0
Bank Sta=5002.7,5006.8
Exp/Cntr=0.3,0.1

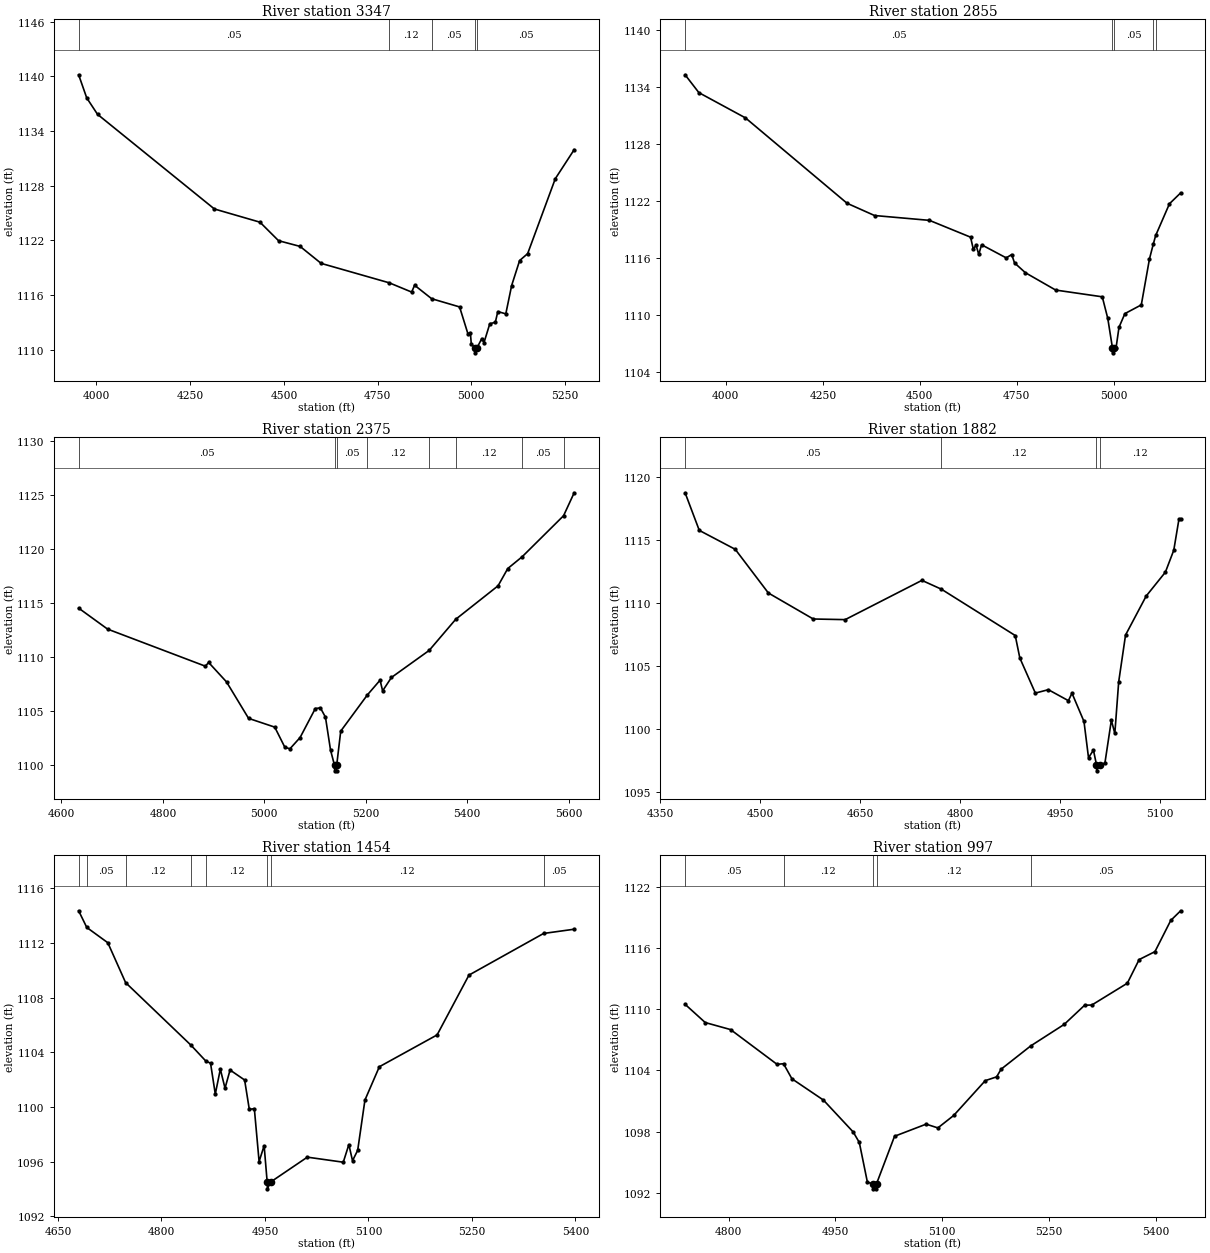
Type RM Length L Ch R = 1,3347,492,492,492
BEGIN DESCRIPTION:
LITTLE LLANO 026 7.0
END DESCRIPTION:
XS GIS Cut Line= 3
      2824705.68     10222303.11      2825363.75     10221488.00
      2825505.66     10221253.15
#Sta/Elev= 30
  3952.4 1140.18  3974.0 1137.64  4002.8 1135.84  4314.6 1125.45  4436.2 1124.00
  4485.7 1121.97  4543.3 1121.34  4599.3 1119.48  4781.5 1117.34  4840.8 1116.33
  4848.7 1117.08  4894.2 1115.60  4968.7 1114.70  4991.1 1111.73  4997.5 1111.88
  4999.9 1110.64  5010.4 1110.16  5010.7 1109.66  5014.5 1110.16  5028.0 1111.23
  5033.8 1110.78  5049.3 1112.85  5064.1 1113.02  5070.7 1114.19  5092.0 1113.94
  5107.6 1117.05  5128.9 1119.79  5150.3 1120.55  5224.0 1128.77  5274.4 1131.96
#Mann=5,-1,0
  3952.4    0.05       0  4781.5    0.12       0  4894.2    0.05       0
  5010.4    0.05       0  5014.5    0.05       0
Bank Sta=5010.4,5014.5
Exp/Cntr=0.3,0.1

Type RM Length L Ch R = 1,2855,480,480,480
BEGIN DESCRIPTION:
LITTLE LLANO 026 6.0
END DESCRIPTION:
XS GIS Cut Line= 3
      2824955.65     10222453.14      2825762.50     10221698.00
      2825855.70     10221553.08
#Sta/Elev= 30
  3894.9 1135.29  3930.4 1133.41  4050.5 1130.75  4312.4 1121.76  4383.2 1120.47
  4524.8 1119.96  4630.8 1118.19  4637.7 1116.95  4645.0 1117.33  4651.9 1116.38
  4659.2 1117.39  4722.7 1116.01  4736.8 1116.36  4744.1 1115.48  4772.0 1114.45
  4850.2 1112.62  4970.3 1111.91  4984.5 1109.63  4996.6 1106.51  4996.9 1106.01
  5000.8 1106.51  5005.9 1106.56  5013.4 1108.70  5028.6 1110.14  5070.9 1111.06
  5092.0 1115.91  5102.0 1117.49  5108.0 1118.37  5143.5 1121.71  5172.3 1122.85
#Mann=5,-1,0
  3894.9    0.05       0  4996.6    0.05       0  5000.8    0.05       0
  5102.0    0.12       0  5108.0    0.05       0
Bank Sta=4996.6,5000.8
Exp/Cntr=0.3,0.1

Type RM Length L Ch R = 1,2375,493,493,493
BEGIN DESCRIPTION:
LITTLE LLANO 026 5.0
END DESCRIPTION:
XS GIS Cut Line= 3
      2825805.65     10222203.14      2826095.25     10221979.00
      2826705.67     10222003.11
#Sta/Elev= 30
  4633.8 1114.51  4690.9 1112.57  4883.8 1109.14  4890.1 1109.49  4925.4 1107.69
  4968.9 1104.32  5020.5 1103.51  5040.5 1101.64  5050.5 1101.51  5070.5 1102.55
  5100.5 1105.23  5110.5 1105.29  5120.5 1104.43  5130.5 1101.39  5138.4 1099.97
  5138.7 1099.47  5142.4 1099.47  5142.6 1099.97  5150.6 1103.14  5203.2 1106.49
  5228.2 1107.85  5233.2 1106.86  5250.6 1108.10  5325.0 1110.60  5377.4 1113.48
  5460.8 1116.57  5480.0 1118.17  5508.4 1119.26  5590.0 1123.05  5610.9 1125.17
#Mann=8,-1,0
  4633.8    0.05       0  5138.4    0.05       0  5142.6    0.05       0
  5203.2    0.12       0  5325.0    0.05       0  5377.4    0.12       0
  5508.4    0.05       0  5590.0    0.12       0
Bank Sta=5138.4,5142.6
Exp/Cntr=0.3,0.1

Type RM Length L Ch R = 1,1882,428,428,428
BEGIN DESCRIPTION:
LITTLE LLANO 026 4.0
END DESCRIPTION:
XS GIS Cut Line= 3
      2825755.73     10222503.09      2826329.00     10222286.00
      2826455.70     10222253.11
#Sta/Elev= 30
  4387.0 1118.73  4408.3 1115.75  4462.3 1114.25  4512.0 1110.79  4579.4 1108.73
  4627.3 1108.68  4742.5 1111.79  4771.8 1111.09  4882.6 1107.42  4889.5 1105.64
  4912.8 1102.86  4932.3 1103.13  4962.4 1102.26  4967.8 1102.85  4985.8 1100.61
  4992.6 1097.74  5000.0 1098.34  5004.5 1097.20  5004.9 1096.70  5009.3 1097.20
  5017.2 1097.31  5026.9 1100.71  5032.1 1099.66  5037.9 1103.75  5048.2 1107.46
  5079.2 1110.55  5108.0 1112.44  5120.6 1114.18  5128.3 1116.62  5130.9 1116.62
#Mann=4,-1,0
  4387.0    0.05       0  4771.8    0.12       0  5004.5    0.07       0
  5009.3    0.12       0
Bank Sta=5004.5,5009.3
Exp/Cntr=0.3,0.1

Type RM Length L Ch R = 1,1454,457,457,457
BEGIN DESCRIPTION:
LITTLE LLANO 026 3.0
END DESCRIPTION:
XS GIS Cut Line= 3
      2826055.66     10222853.14      2826275.00     10222620.00
      2826655.66     10222503.12
#Sta/Elev= 30
  4679.9 1114.36  4691.7 1113.14  4722.2 1112.02  4748.0 1109.10  4842.7 1104.52
  4864.4 1103.35  4871.1 1103.20  4878.0 1100.94  4885.3 1102.76  4892.1 1101.37
  4899.4 1102.70  4920.5 1101.97  4927.3 1099.82  4934.6 1099.87  4941.5 1096.00
  4948.8 1097.16  4953.2 1094.50  4953.6 1094.00  4958.2 1094.50  5011.4 1096.32
  5063.5 1095.95  5071.6 1097.24  5076.9 1096.06  5084.4 1096.82  5094.9 1100.50
  5115.8 1102.94  5199.5 1105.27  5245.7 1109.65  5353.9 1112.70  5398.2 1113.01
#Mann=8,-1,0
  4679.9    0.12       0  4691.7    0.05       0  4748.0    0.12       0
  4842.7    0.05       0  4864.4    0.12       0  4953.2    0.07       0
  4958.2    0.12       0  5353.9    0.05       0
Bank Sta=4953.2,4958.2
Exp/Cntr=0.3,0.1

Type RM Length L Ch R = 1,997,409,409,409
BEGIN DESCRIPTION:
LITTLE LLANO 026 2.0
END DESCRIPTION:
XS GIS Cut Line= 3
      2826255.69     10223103.11      2826468.50     10222952.00
      2826855.70     10222753.10
#Sta/Elev= 30
  4739.0 1110.49  4767.3 1108.70  4802.9 1108.01  4868.2 1104.60  4877.3 1104.66
  4889.1 1103.18  4933.4 1101.09  4975.2 1097.96  4983.8 1096.93  4995.2 1093.02
  5003.0 1092.88  5003.3 1092.38  5007.6 1092.38  5008.0 1092.88  5033.3 1097.54
  5077.7 1098.73  5094.2 1098.36  5116.4 1099.58  5160.8 1103.00  5176.7 1103.37
  5183.0 1104.12  5224.7 1106.41  5271.7 1108.52  5300.4 1110.40  5310.5 1110.42
  5360.4 1112.56  5377.0 1114.88  5399.2 1115.66  5421.4 1118.72  5435.3 1119.67
#Mann=5,-1,0
  4739.0    0.05       0  4877.3    0.12       0  5003.0    0.07       0
  5008.0    0.12       0  5224.7    0.05       0
Bank Sta=5003,5008
Exp/Cntr=0.3,0.1