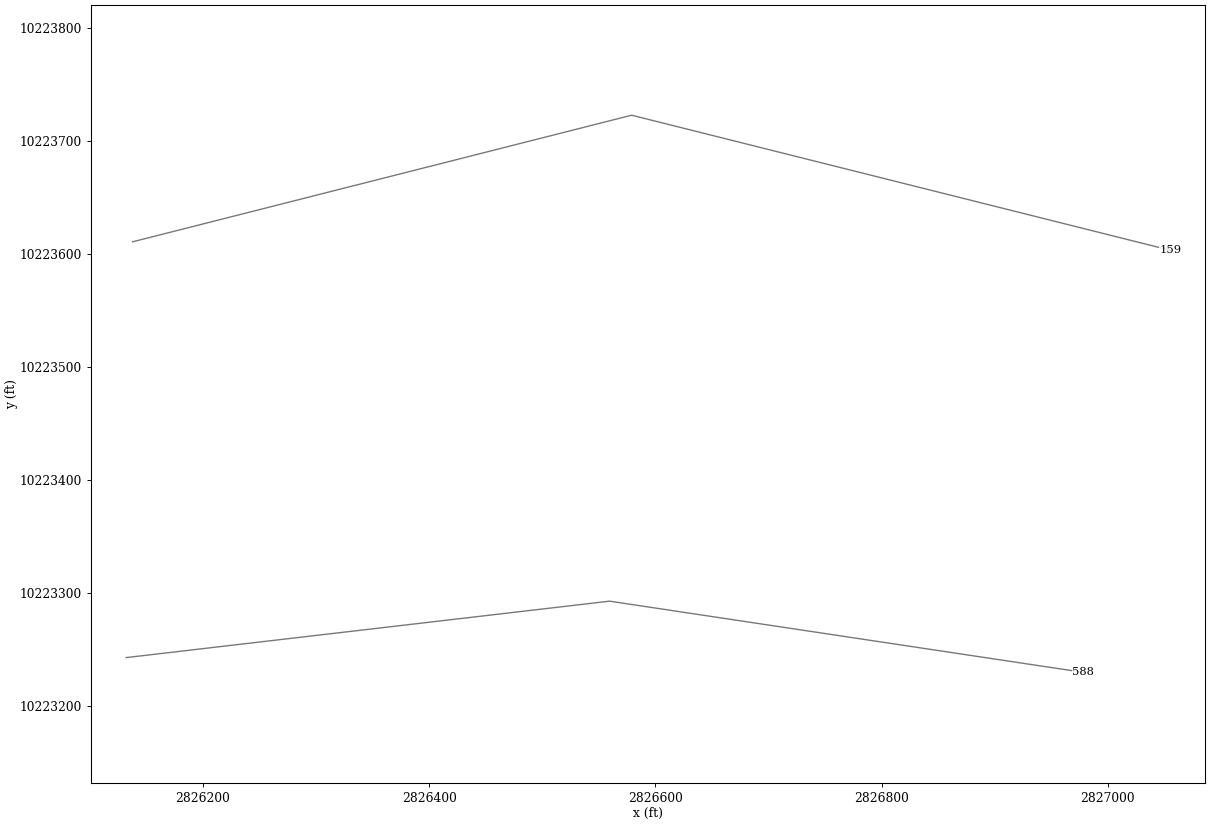
HEC-RAS study LITTLE LLANO 026.prj: LITTLE LLANO 026 Base Level Engineering

--- LITTLE LLANO 026.g01 (geometry) --- (continued)

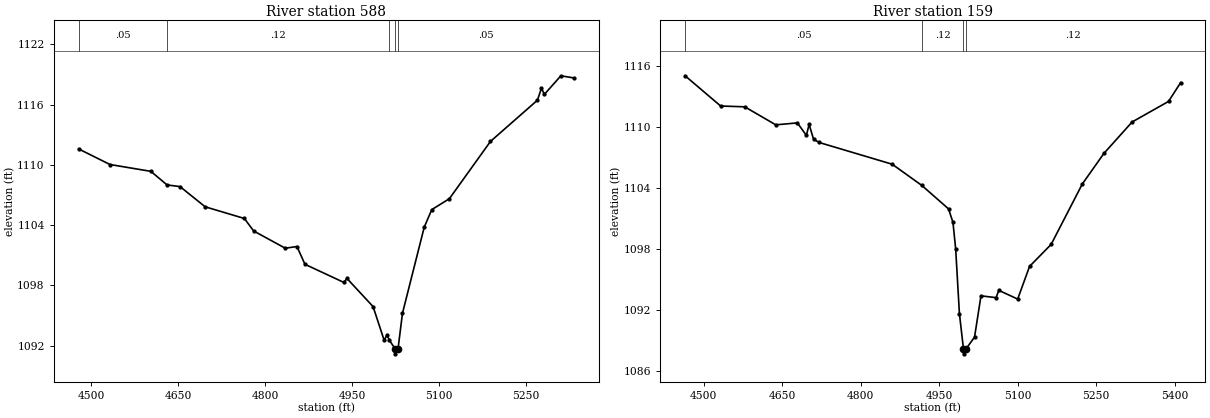
Type RM Length L Ch R = 1,588,429,429,429
BEGIN DESCRIPTION:
Mapping XS bc52b8c1
END DESCRIPTION:
XS GIS Cut Line= 3
      2826132.03     10223243.05      2826559.50     10223292.95
      2826978.32     10223230.02
#Sta/Elev= 30
  4478.7 1111.58  4532.7 1110.03  4603.2 1109.35  4631.0 1108.00  4653.5 1107.83
  4696.8 1105.82  4764.3 1104.66  4780.2 1103.42  4834.8 1101.70  4854.9 1101.87
  4868.7 1100.10  4935.6 1098.30  4941.1 1098.69  4986.1 1095.89  5005.1 1092.55
  5010.2 1093.06  5014.3 1092.53  5024.1 1091.69  5024.4 1091.19  5029.1 1091.69
  5036.7 1095.22  5074.2 1103.79  5087.2 1105.54  5117.6 1106.63  5188.4 1112.33
  5269.3 1116.43  5276.2 1117.62  5281.3 1117.01  5309.7 1118.86  5332.6 1118.64
#Mann=5,-1,0
  4478.7    0.05       0  4631.0    0.12       0  5014.3    0.05       0
  5024.1    0.07       0  5029.1    0.05       0
Bank Sta=5024.1,5029.1
Exp/Cntr=0.3,0.1

Type RM Length L Ch R = 1,159,0,0,0
BEGIN DESCRIPTION:
LITTLE LLANO 026 1.0
END DESCRIPTION:
XS GIS Cut Line= 3
      2826137.78     10223610.70      2826579.03     10223722.64
      2827055.64     10223603.12
#Sta/Elev= 30
  4464.8 1115.05  4532.7 1112.08  4578.8 1112.00  4638.0 1110.23  4679.3 1110.42
  4696.5 1109.19  4701.7 1110.27  4710.2 1108.82  4720.6 1108.50  4860.4 1106.36
  4916.9 1104.28  4968.1 1101.97  4976.5 1100.64  4981.7 1098.01  4988.8 1091.69
  4996.5 1088.23  4996.9 1087.73  5001.6 1088.23  5017.7 1089.37  5030.0 1093.43
  5058.9 1093.25  5064.0 1093.97  5100.1 1093.11  5122.8 1096.32  5164.0 1098.48
  5223.6 1104.42  5264.8 1107.42  5318.7 1110.51  5388.3 1112.53  5411.4 1114.38
#Mann=4,-1,0
  4464.8    0.05       0  4916.9    0.12       0  4996.5    0.07       0
  5001.6    0.12       0
Bank Sta=4996.5,5001.6
Exp/Cntr=0.3,0.1

Chan Stop Cuts=-1