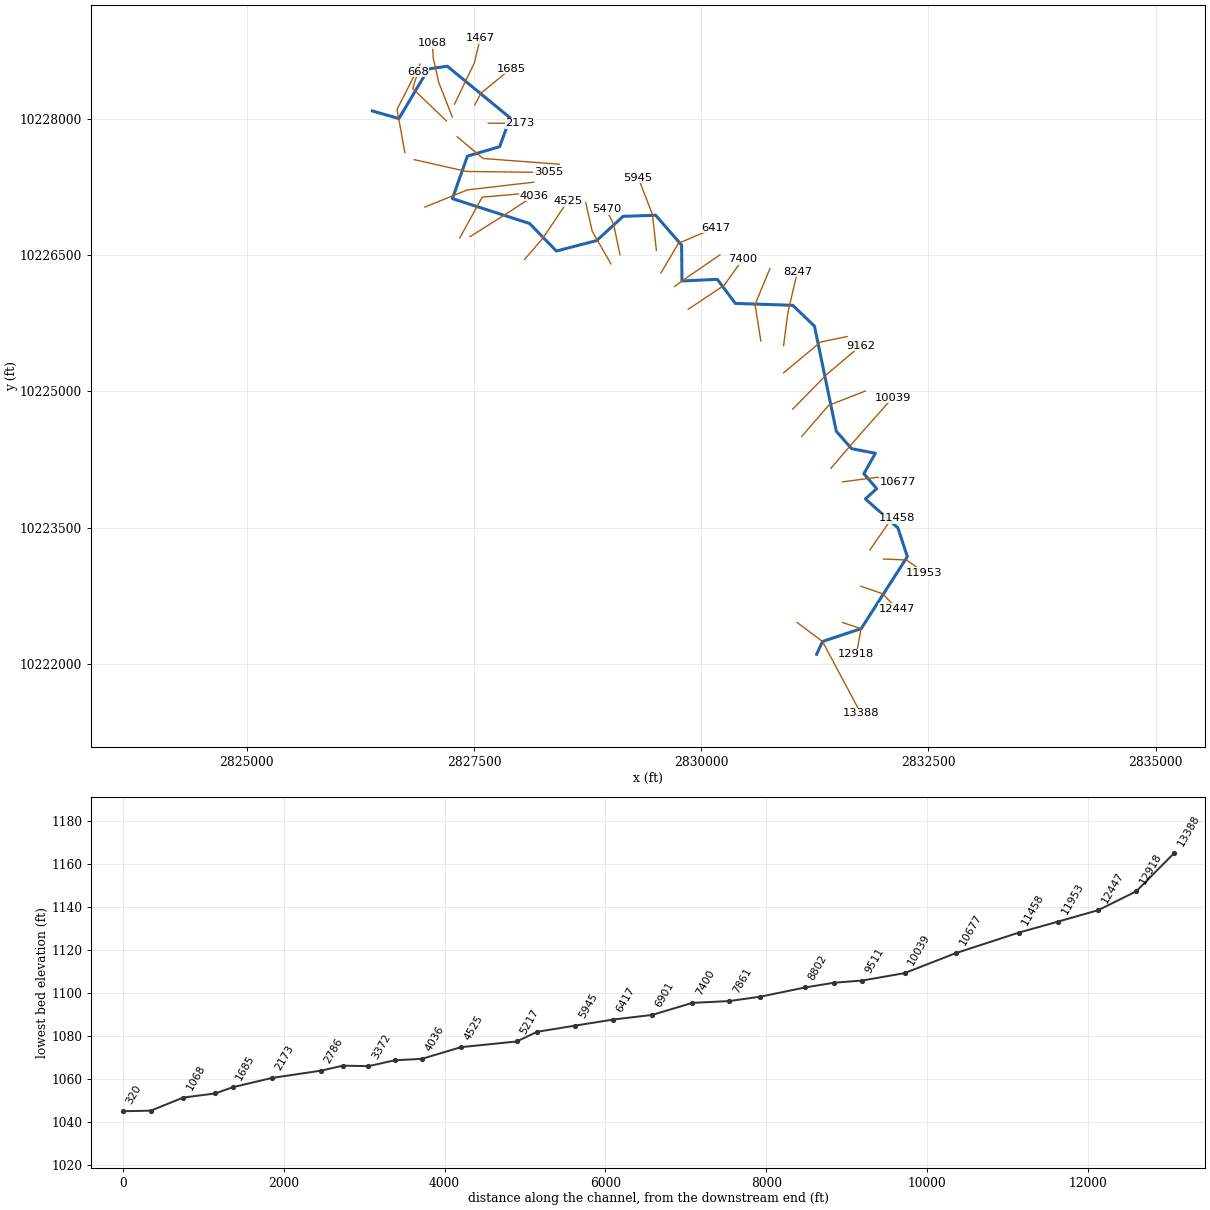
--- LITTLE LLANO 027.prj (project) ---

Proj Title=LITTLE LLANO 027 Base Level Engineering
Current Plan=p01
Default Exp/Contr=0.3,0.1
English Units
Geom File=g01
Flow File=f01
Plan File=p01
Y Axis Title=Elevation
X Axis Title(PF)=Main Channel Distance
X Axis Title(XS)=Station
BEGIN DESCRIPTION:
LITTLE LLANO 027
END DESCRIPTION:
DSS Export Rating Curves= 0
DSS Export Rating Curve Sorted= 0
DSS Export Volume Flow Curves= 0
DXF OffsetX= 0
DXF OffsetY= 0
DXF ScaleX= 1
DXF ScaleY= 10

--- LITTLE LLANO 027.p01 (plan) ---

Plan Title=Multiple Run
Short Identifier=Multiple
Geom File=g01
Flow File=f01
Subcritical Flow
K Sum by GR= 0
Std Step Tol= 0.01
Critical Tol= 0.01
Num of Std Step Trials= 20
Max Error Tol= 0.3
Flow Tol Ratio= 0.001
Split Flow NTrial= 30
Split Flow Tol= 0.02
Split Flow Ratio= 0.02
Log Output Level= 0
Friction Slope Method= 1
Unsteady Friction Slope Method= 2
Unsteady Bridges Friction Slope Method= 1
Parabolic Critical Depth
Global Vel Dist=  1 , 1 , 1
Global Log Level= 0
CheckData=True
Encroach Param= -1, 0, 0, 0
BEGIN DESCRIPTION:
Multiple Run
END DESCRIPTION:

--- LITTLE LLANO 027.f01 (steady flow) ---

Flow Title=Multiple
Number of Profiles=7
Profile Names=10-year,25-year,50-year,1pct_min,100-year,1pct_plu,500-year
River Rch & RM= LITTLE LLANO 027,Reach-1,13388
     140     210     250     202     319     502     440
River Rch & RM= LITTLE LLANO 027,Reach-1,10039
    1043    1794    4331    3255    6379   12500    9407
River Rch & RM= LITTLE LLANO 027,Reach-1,5470
    1246    2176    4951    3582    7295   14857   10706
Boundary for River Rch & Prof#=LITTLE LLANO 027,Reach-1,1
Up Type=0
Dn Type=3
Dn Slope=0.005
Boundary for River Rch & Prof#=LITTLE LLANO 027,Reach-1,2
Up Type=0
Dn Type=3
Dn Slope=0.005
Boundary for River Rch & Prof#=LITTLE LLANO 027,Reach-1,3
Up Type=0
Dn Type=3
Dn Slope=0.005
Boundary for River Rch & Prof#=LITTLE LLANO 027,Reach-1,4
Up Type=0
Dn Type=3
Dn Slope=0.005
Boundary for River Rch & Prof#=LITTLE LLANO 027,Reach-1,5
Up Type=0
Dn Type=3
Dn Slope=0.005
Boundary for River Rch & Prof#=LITTLE LLANO 027,Reach-1,6
Up Type=0
Dn Type=3
Dn Slope=0.005
Boundary for River Rch & Prof#=LITTLE LLANO 027,Reach-1,7
Up Type=0
Dn Type=3
Dn Slope=0.005

--- LITTLE LLANO 027.g01 (geometry) ---

Geom Title=Existing Conditions
Program Version=4.10

River Reach=LITTLE LLANO 027,Reach-1
Reach XY= 30
       2831269.5       10222104.        2831334.       10222245.
      2831759.25       10222386.      2832267.75       10223179.
      2832164.25       10223495.        2831806.       10223815.
      2831930.25       10223928.      2831789.25       10224092.
      2831915.75       10224318.      2831654.75       10224368.
      2831485.75       10224560.       2831245.5       10225718.
       2831006.5       10225947.       2830375.5       10225968.
      2830176.25       10226233.       2829787.5       10226215.
       2829783.5       10226610.       2829497.5       10226939.
        2829140.       10226927.      2828849.25       10226660.
       2828405.5       10226545.       2828110.5       10226848.
      2827261.25       10227122.      2827426.25       10227590.
      2827781.25       10227694.        2827897.       10228011.
      2827205.25       10228580.      2826997.25       10228550.
       2826672.5       10228004.      2826380.75       10228087.

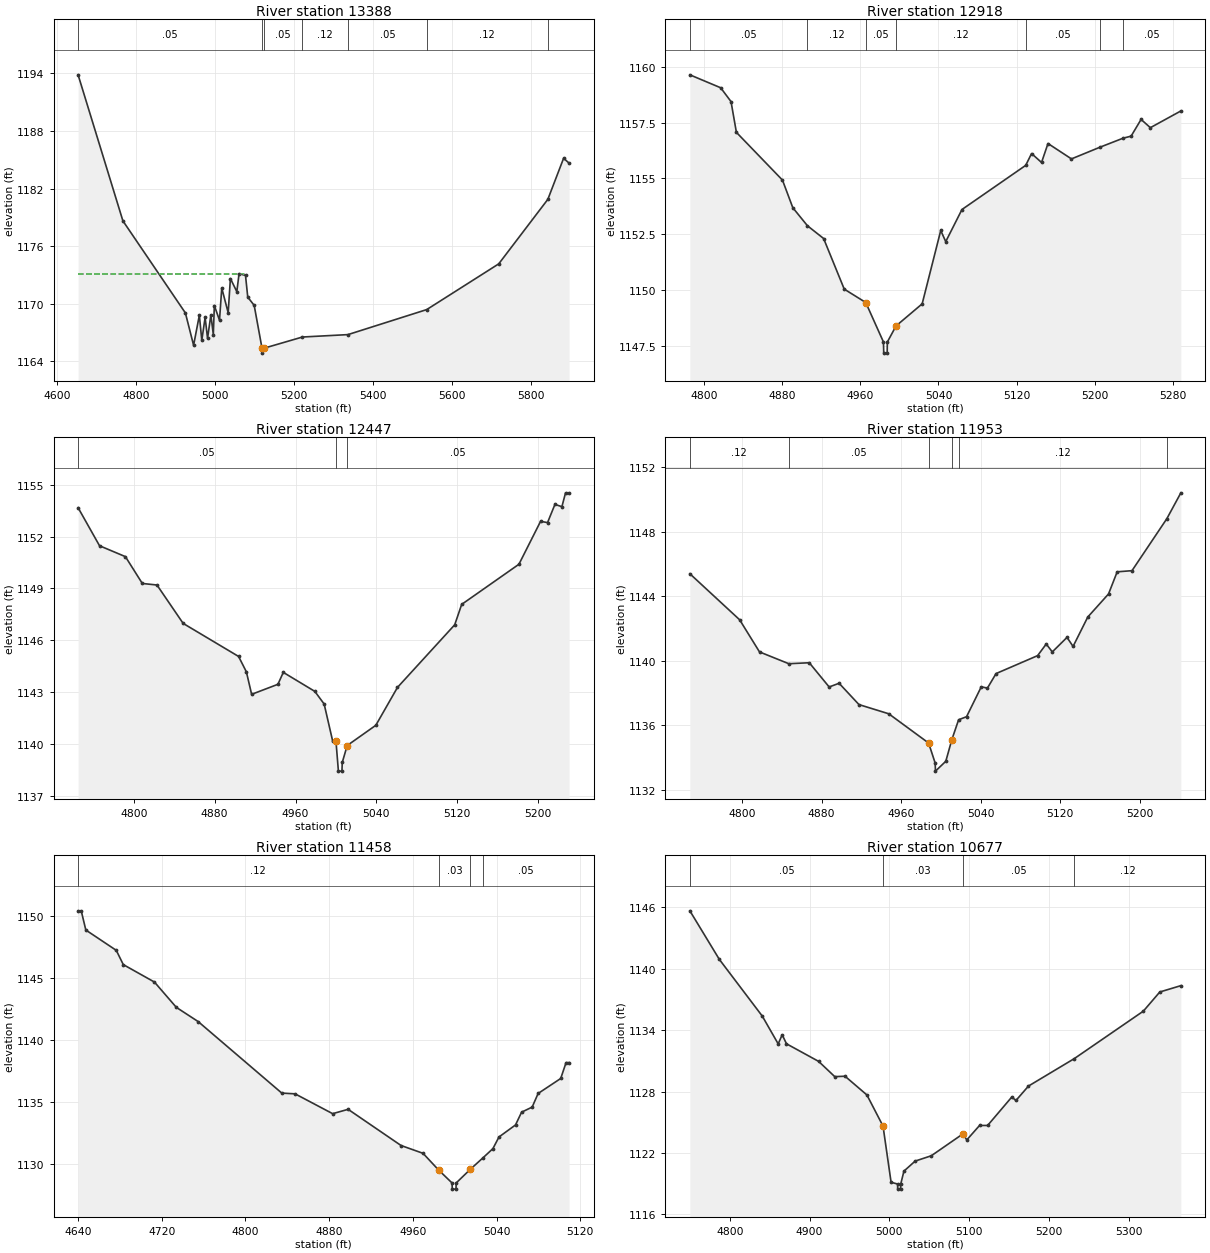
Type RM Length L Ch R = 1 ,13388   ,470,470,470
BEGIN DESCRIPTION:
LITTLE LLANO 027 28.0
END DESCRIPTION:
XS GIS Cut Line= 3
       2831055.7      10222453.1        2831334.       10222245.
       2831755.7     10221453.08
#Sta/Elev= 30
  4652.5 1193.86  4766.1 1178.63  4924.5 1169.03  4945.3 1165.66  4959.9 1168.79
  4966.1 1166.17  4974.5 1168.56  4980.7 1166.38  4989.1 1168.82  4995.3 1166.78
  4997.9  1169.8    5011 1168.27  5016.7 1171.63    5033 1169.05  5038.6 1172.62
  5054.9 1171.25  5060.6 1173.13  5076.9 1172.94  5082.6 1170.68  5098.9 1169.82
  5118.8 1165.34  5119.1 1164.84  5122.8 1165.34  5221.2 1166.52  5336.5 1166.77
  5536.3 1169.38  5718.9 1174.15  5843.4 1180.88  5883.3 1185.16  5897.2 1184.65
#Mann= 7 ,-1 , 0
  4652.5     .05       0  5118.8     .05       0  5122.8     .05       0
  5221.2     .12       0  5336.5     .05       0  5536.3     .12       0
  5843.4     .05       0
#XS Ineff= 2 , 0
          5072.5 1173.08
Permanent Ineff=
       F       F
Bank Sta=5118.8,5122.8
XS Rating Curve= 0 ,0
Exp/Cntr=0.3,0.1

Type RM Length L Ch R = 1 ,12918   ,471,471,471
BEGIN DESCRIPTION:
LITTLE LLANO 027 27.0
END DESCRIPTION:
XS GIS Cut Line= 3
      2831555.73      10222453.1      2831759.25       10222386.
      2831705.69     10222103.13
#Sta/Elev= 30
  4785.7 1159.64  4817.2 1159.06  4827.8 1158.44  4833.3 1157.06  4880.4 1154.92
    4891 1153.68    4906 1152.87  4922.5  1152.3  4943.6 1150.03  4965.6 1149.43
  4983.7 1147.66    4984 1147.16  4987.5 1147.16  4987.7 1147.66  4996.6 1148.38
  5023.3 1149.37  5042.3 1152.66  5047.4 1152.16    5064  1153.6  5129.2 1155.58
  5135.2 1156.11  5145.4 1155.71    5152 1156.56    5176 1155.87  5205.5  1156.4
  5228.9  1156.8    5237 1156.89  5247.2 1157.64  5256.7 1157.27  5287.9 1158.02
#Mann= 7 ,-1 , 0
  4785.7     .05       0    4906     .12       0  4965.6     .05       0
  4996.6     .12       0  5129.2     .05       0  5205.5     .12       0
  5228.9     .05       0
Bank Sta=4965.6,4996.6
XS Rating Curve= 0 ,0
Exp/Cntr=0.3,0.1

Type RM Length L Ch R = 1 ,12447   ,494,494,494
BEGIN DESCRIPTION:
LITTLE LLANO 027 26.0
END DESCRIPTION:
XS GIS Cut Line= 3
      2831755.68     10222853.11      2831996.75       10222770.
      2832155.71     10222603.08
#Sta/Elev= 30
    4745 1153.67  4766.2 1151.47  4791.8 1150.84  4808.5 1149.29    4823  1149.2
  4848.9 1146.98  4903.7 1145.07  4911.4 1144.18  4916.6 1142.88  4942.6 1143.46
  4947.9 1144.15  4979.1 1143.05  4988.3 1142.32  4996.8 1140.16    5000 1140.16
  5002.4 1138.44  5005.9 1138.44  5006.2 1138.94  5011.1 1139.92  5039.4 1141.09
  5060.8 1143.28  5117.4  1146.9  5124.3 1148.08  5180.9  1150.4  5202.3 1152.88
  5209.2 1152.81  5216.5 1153.86  5223.4 1153.73    5227 1154.53  5230.5 1154.53
#Mann= 3 , 0 , 0
    4745     .05       0    5000     .05       0  5011.1     .05       0
Bank Sta=5000,5011.1
XS Rating Curve= 0 ,0
Exp/Cntr=0.3,0.1

Type RM Length L Ch R = 1 ,11953   ,495,495,495
BEGIN DESCRIPTION:
LITTLE LLANO 027 25.0
END DESCRIPTION:
XS GIS Cut Line= 3
      2832005.64     10223153.11        2832258.       10223142.
      2832455.69     10223003.11
#Sta/Elev= 30
  4747.4 1145.39  4797.5 1142.54  4817.5 1140.55    4847 1139.82  4867.6 1139.88
  4887.6 1138.38  4897.6 1138.61  4917.6 1137.29  4947.6 1136.72  4987.7 1134.91
  4994.3 1133.67  4994.6 1133.17    5005 1133.78  5011.1 1135.12  5017.9 1136.35
  5025.9 1136.54  5040.7 1138.39  5046.9 1138.31  5055.6 1139.21  5097.4 1140.32
  5106.1 1141.04  5112.2 1140.55    5127 1141.45  5133.1 1140.89  5147.9 1142.71
  5168.8 1144.14  5177.5 1145.51  5192.4 1145.58  5227.5  1148.8  5241.6  1150.4
#Mann= 6 ,-1 , 0
  4747.4     .12       0    4847     .05       0  4987.7     .03       0
  5011.1     .05       0  5017.9     .12       0  5227.5     .05       0
Bank Sta=4987.7,5011.1
XS Rating Curve= 0 ,0
Exp/Cntr=0.3,0.1

Type RM Length L Ch R = 1 ,11458   ,781,781,781
BEGIN DESCRIPTION:
LITTLE LLANO 027 24.0
END DESCRIPTION:
XS GIS Cut Line= 3
      2831855.69     10223253.11      2832060.75       10223549.
      2832155.71     10223603.13
#Sta/Elev= 30
    4640 1150.45    4643 1150.45  4647.4  1148.9  4676.5 1147.26  4683.2 1146.11
    4713  1144.7  4733.9 1142.66  4754.8 1141.51  4834.7 1135.74  4847.4 1135.68
  4883.3 1134.08  4898.1 1134.43  4948.7 1131.51  4969.7 1130.88  4984.5 1129.54
  4997.4 1128.49  4997.7 1127.99  5001.2 1127.99  5001.4 1128.49  5014.9 1129.59
  5027.3 1130.54  5036.5 1131.26  5042.3  1132.2  5058.1 1133.17  5063.9  1134.2
    5074 1134.61  5079.7 1135.71  5101.3 1136.92  5106.4  1138.2  5109.3  1138.2
#Mann= 4 ,-1 , 0
    4640     .12       0  4984.5     .03       0  5014.9     .12       0
  5027.3     .05       0
Bank Sta=4984.5,5014.9
XS Rating Curve= 0 ,0
Exp/Cntr=0.3,0.1

Type RM Length L Ch R = 1 ,10677   ,638,638,638
BEGIN DESCRIPTION:
LITTLE LLANO 027 23.0
END DESCRIPTION:
XS GIS Cut Line= 3
      2831555.65     10224003.11      2831938.67     10224053.32
      2832161.33     10223999.34
#Sta/Elev= 30
  4749.9 1145.66  4786.8 1140.92  4840.7 1135.37  4860.6 1132.66  4865.6 1133.55
    4871 1132.67  4911.3 1130.95  4931.5 1129.46  4944.4  1129.5  4971.8 1127.67
    4992 1124.63  5002.1 1119.14  5010.2 1118.97  5010.4 1118.47  5013.9 1118.47
  5014.2 1118.97  5018.2 1120.23  5032.3 1121.21  5052.5 1121.73    5092 1123.86
    5097 1123.28    5113 1124.69  5123.1 1124.69  5153.4 1127.47  5158.6 1127.13
  5174.3 1128.54  5231.7 1131.22  5318.3 1135.86  5338.9 1137.73  5365.3 1138.35
#Mann= 4 ,-1 , 0
  4749.9     .05       0    4992     .03       0    5092     .05       0
  5231.7     .12       0
Bank Sta=4992,5092
XS Rating Curve= 0 ,0
Exp/Cntr=0.3,0.1

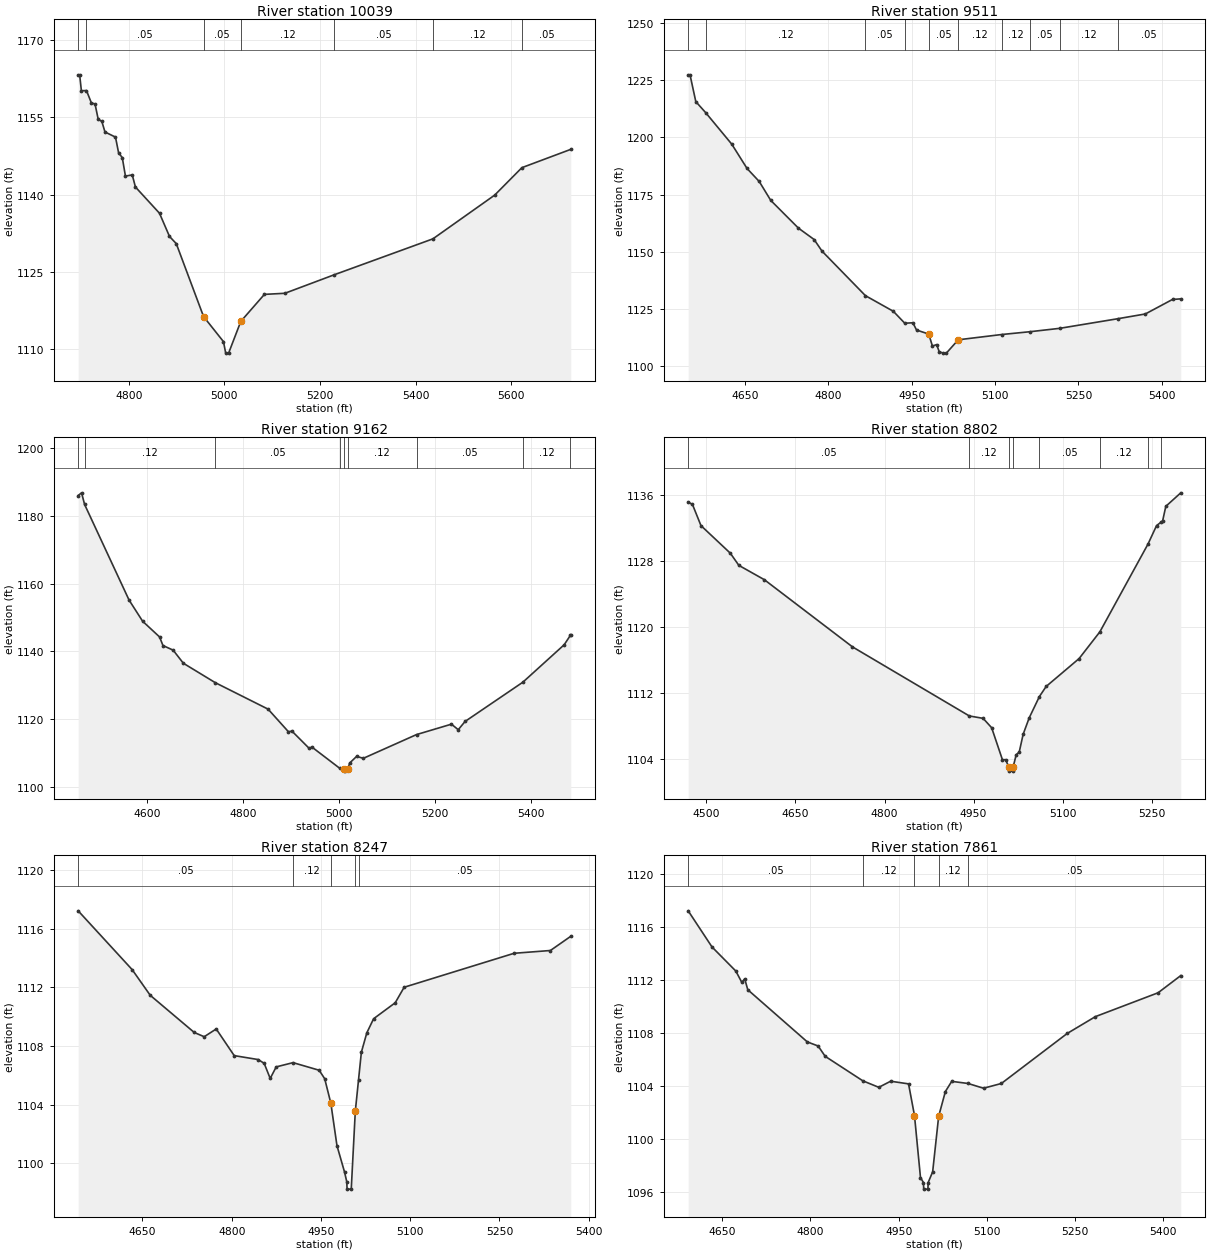
Type RM Length L Ch R = 1 ,10039   ,528,528,528
BEGIN DESCRIPTION:
LITTLE LLANO 027 22.0
END DESCRIPTION:
XS GIS Cut Line= 3
      2831426.69     10224152.54      2831744.71     10224522.42
      2832105.46     10224928.27
#Sta/Elev= 30
  4694.1  1163.3  4697.2  1163.3  4700.8 1160.22  4711.5 1160.23  4721.7 1157.85
  4729.4 1157.62    4736 1154.66  4743.6 1154.24  4750.2 1152.18  4772.2 1151.18
  4778.7 1148.13  4786.4 1147.19    4793 1143.61  4807.3 1143.82  4813.9 1141.48
  4864.3 1136.37  4885.2 1131.86  4899.4 1130.46  4956.5 1116.27  4998.2 1111.39
  5002.8 1109.16  5008.9 1109.16  5034.4 1115.33  5083.8 1120.59  5126.6  1120.8
  5229.5 1124.39  5436.4 1131.39  5565.7  1139.9  5622.6 1145.24  5724.9  1148.8
#Mann= 7 ,-1 , 0
  4694.1     .12       0  4711.5     .05       0  4956.5     .05       0
  5034.4     .12       0  5229.5     .05       0  5436.4     .12       0
  5622.6     .05       0
Bank Sta=4956.5,5034.4
XS Rating Curve= 0 ,0
Exp/Cntr=0.3,0.1

Type RM Length L Ch R = 1 ,9511    ,349,349,349
BEGIN DESCRIPTION:
LITTLE LLANO 027 21.0
END DESCRIPTION:
XS GIS Cut Line= 3
      2831105.68     10224503.11       2831401.5       10224845.
      2831805.68     10225003.11
#Sta/Elev= 30
  4547.9 1227.39  4551.2 1227.39  4561.6 1215.68  4579.2  1210.9  4626.3 1197.07
  4653.8 1186.44  4675.7 1180.75  4696.5 1172.47  4746.3 1160.34  4774.4 1155.39
  4788.7 1150.29  4866.7 1130.84  4916.9    1124  4937.5 1118.79  4952.1 1118.98
  4958.7  1115.8  4980.6 1114.05  4987.2 1108.83  4994.8 1109.43  4999.4 1106.39
  5006.1 1105.71  5012.3 1105.71  5033.7 1111.54  5111.9 1113.85  5162.7 1115.07
  5216.2 1116.55  5320.4 1120.74  5370.2 1122.83  5419.1 1129.18    5434 1129.44
#Mann= 10 ,-1 , 0
  4547.9     .05       0  4579.2     .12       0  4866.7     .05       0
  4937.5     .12       0  4980.6     .05       0  5033.7     .12       0
  5111.9     .12       0  5162.7     .05       0  5216.2     .12       0
  5320.4     .05       0
Bank Sta=4980.6,5033.7
XS Rating Curve= 0 ,0
Exp/Cntr=0.3,0.1

Type RM Length L Ch R = 1 ,9162    ,360,360,360
BEGIN DESCRIPTION:
LITTLE LLANO 027 20.0
END DESCRIPTION:
XS GIS Cut Line= 3
      2831005.67      10224803.1       2831386.5       10225191.
      2831755.66     10225503.09
#Sta/Elev= 30
  4456.4    1186  4463.5 1186.79  4469.8 1183.36  4562.5 1155.16  4590.8 1148.91
  4626.1 1144.28  4633.2 1141.74  4654.4 1140.39  4675.7 1136.52  4742.3 1130.79
  4852.4 1122.98  4894.8 1116.31    4902 1116.52  4937.2 1111.53  4944.4 1111.73
  5001.5 1105.56  5011.2  1105.2  5011.7  1104.7  5018.4  1105.2  5022.5  1107.1
  5036.8 1109.03  5051.1 1108.49  5161.8 1115.48  5234.6 1118.55  5248.8 1116.92
  5263.1 1119.36  5383.5 1130.93  5469.7 1141.98  5482.5 1144.73  5483.4 1144.73
#Mann= 9 ,-1 , 0
  4456.4     .05       0  4469.8     .12       0  4742.3     .05       0
  5001.5     .12       0  5011.2     .03       0  5018.4     .12       0
  5161.8     .05       0  5383.5     .12       0  5482.5     .05       0
Bank Sta=5011.2,5018.4
XS Rating Curve= 0 ,0
Exp/Cntr=0.3,0.1

Type RM Length L Ch R = 1 ,8802    ,555,555,555
BEGIN DESCRIPTION:
LITTLE LLANO 027 19.0
END DESCRIPTION:
XS GIS Cut Line= 3
      2830905.68     10225203.11        2831313.       10225543.
      2831605.69     10225603.11
#Sta/Elev= 30
  4469.5 1135.17  4476.7 1134.88    4491 1132.31  4540.4 1128.96  4554.8 1127.48
  4597.7 1125.74  4746.1 1117.58  4942.8 1109.19    4966  1108.9  4980.4 1107.76
  4998.5 1103.88  5003.9 1103.88  5009.3 1102.99  5009.8 1102.49  5016.1 1102.49
  5016.6 1102.99  5021.7 1104.48  5026.8  1104.8  5033.4 1106.96  5043.6 1108.96
  5060.8 1111.55  5072.1 1112.77  5127.6 1116.16  5162.6 1119.41  5243.7 1130.08
    5258 1132.31  5266.2 1132.76  5268.2 1132.87  5273.6 1134.65  5298.8 1136.29
#Mann= 8 ,-1 , 0
  4469.5     .05       0  4942.8     .12       0  5009.3     .07       0
  5016.6     .12       0  5060.8     .05       0  5162.6     .12       0
  5243.7     .05       0  5266.2     .12       0
Bank Sta=5009.3,5016.6
XS Rating Curve= 0 ,0
Exp/Cntr=0.3,0.1

Type RM Length L Ch R = 1 ,8247    ,386,386,386
BEGIN DESCRIPTION:
LITTLE LLANO 027 18.0
END DESCRIPTION:
XS GIS Cut Line= 3
      2830905.68     10225503.09      2830953.23     10225867.92
       2831057.4     10226315.85
#Sta/Elev= 30
    4542 1117.23  4632.8 1113.21  4663.1 1111.46  4737.1 1108.92  4753.8 1108.63
    4774 1109.16  4804.2 1107.34  4844.6 1107.07  4854.6 1106.81  4864.7 1105.78
  4874.8 1106.57  4903.1 1106.86    4947 1106.34  4956.3 1105.76  4966.6 1104.09
  4976.9 1101.19  4989.6 1099.39  4993.4 1098.72  4993.9 1098.22  5000.9 1098.22
  5007.7 1103.53  5013.1 1105.67  5017.9 1107.57  5027.1  1108.9  5038.5 1109.86
  5074.8 1110.95  5089.8 1112.01  5274.6 1114.33  5335.6 1114.52  5369.8 1115.49
#Mann= 5 ,-1 , 0
    4542     .05       0  4903.1     .12       0  4966.6     .07       0
  5007.7     .12       0  5013.1     .05       0
Bank Sta=4966.6,5007.7
XS Rating Curve= 0 ,0
Exp/Cntr=0.3,0.1

Type RM Length L Ch R = 1 ,7861    ,461,461,461
BEGIN DESCRIPTION:
LITTLE LLANO 027 17.0
END DESCRIPTION:
XS GIS Cut Line= 3
      2830655.69      10225553.1        2830592.       10225956.
      2830755.68     10226353.09
#Sta/Elev= 30
  4592.1  1117.2  4632.6 1114.47  4673.1 1112.65  4683.2  1111.8  4688.2 1112.06
  4693.4 1111.24  4794.6  1107.3    4813 1106.99    4825 1106.21    4889 1104.36
  4916.1 1103.87  4936.3 1104.33  4966.7 1104.13  4976.8 1101.74    4987 1097.05
    4992 1096.68  4992.5 1096.18  4999.6 1096.18  5000.1 1096.68  5007.7 1097.49
  5017.9 1101.68  5029.3 1103.55  5040.1 1104.32  5067.8 1104.16  5094.2  1103.8
  5124.5 1104.16  5236.5 1107.94  5284.4 1109.21  5390.9 1111.01  5429.5 1112.31
#Mann= 5 ,-1 , 0
  4592.1     .05       0    4889     .12       0  4976.8     .07       0
  5017.9     .12       0  5067.8     .05       0
Bank Sta=4976.8,5017.9
XS Rating Curve= 0 ,0
Exp/Cntr=0.3,0.1

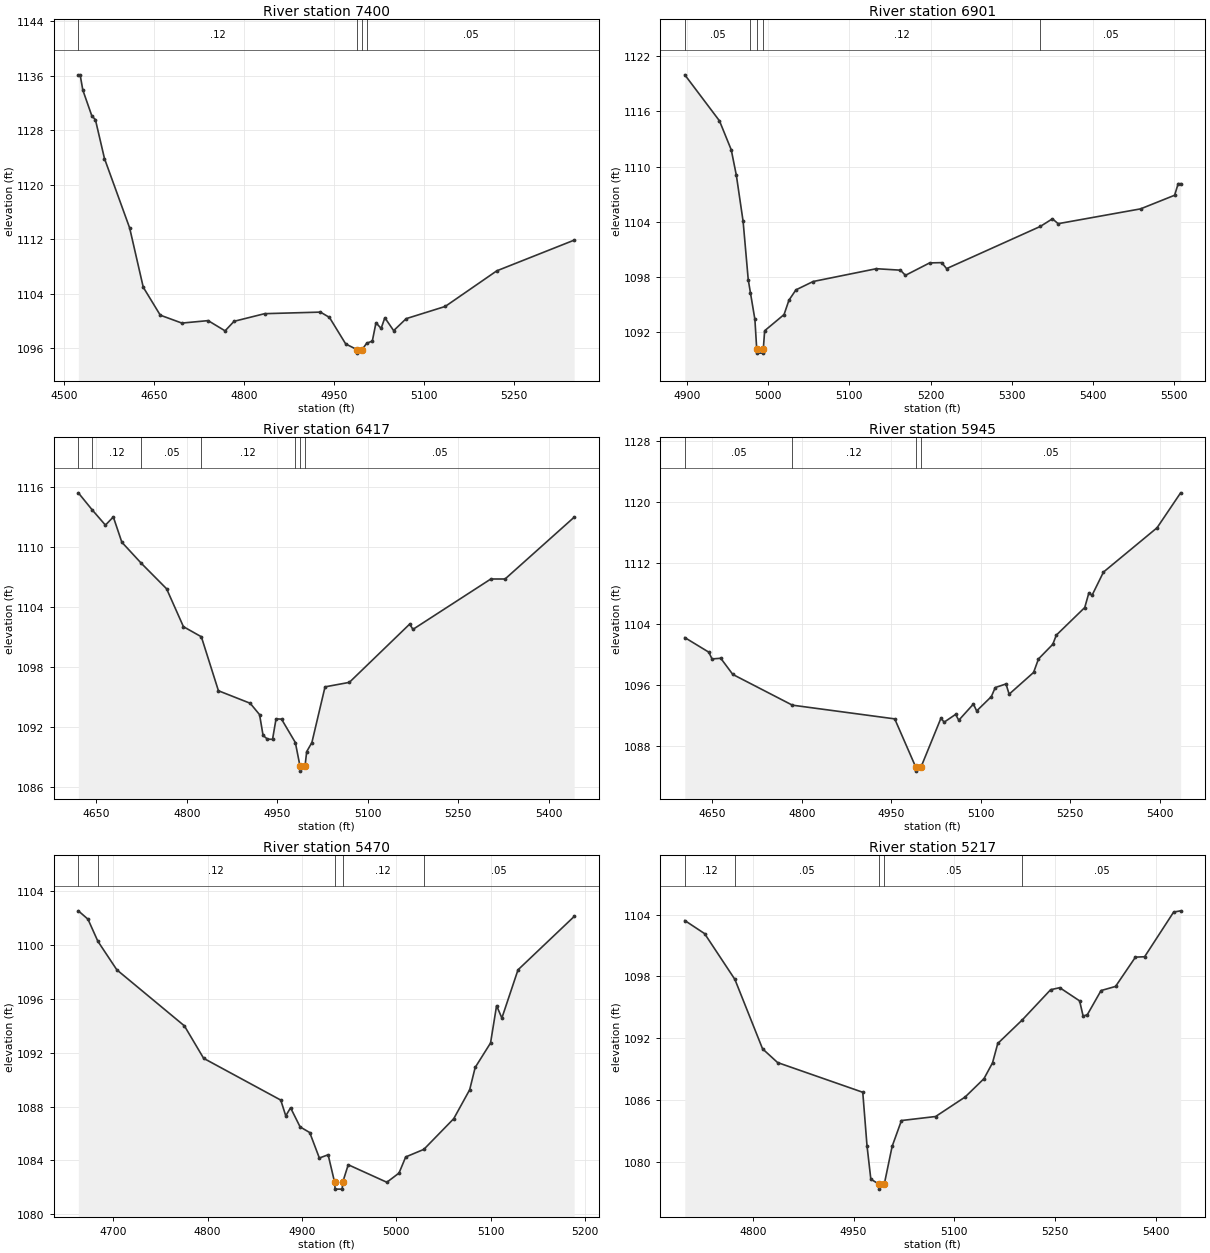
Type RM Length L Ch R = 1 ,7400    ,499,499,499
BEGIN DESCRIPTION:
LITTLE LLANO 027 16.0
END DESCRIPTION:
XS GIS Cut Line= 3
      2829855.67     10225903.11        2830252.       10226168.
      2830455.69     10226453.12
#Sta/Elev= 30
  4523.3 1136.16  4526.3 1136.16  4530.8 1133.92  4545.8 1130.14  4551.8 1129.57
  4566.9 1123.88  4608.9 1113.69  4631.6 1104.99    4660 1100.89    4696 1099.73
  4739.8 1100.09  4768.1 1098.59  4783.1 1099.99  4834.1 1101.11  4927.2 1101.34
  4942.2 1100.56  4969.3 1096.67  4988.4 1095.82  4988.9 1095.32  4996.5 1095.82
  5004.3 1096.77  5013.7 1097.09  5019.8 1099.77  5028.4 1098.95  5034.6 1100.51
  5049.3 1098.62  5070.2 1100.38  5135.3 1102.17  5221.4  1107.4  5350.4  1111.9
#Mann= 4 ,-1 , 0
  4523.3     .12       0  4988.4     .07       0  4996.5     .12       0
  5004.3     .05       0
Bank Sta=4988.4,4996.5
XS Rating Curve= 0 ,0
Exp/Cntr=0.3,0.1

Type RM Length L Ch R = 1 ,6901    ,484,484,484
BEGIN DESCRIPTION:
LITTLE LLANO 027 15.0
END DESCRIPTION:
XS GIS Cut Line= 3
      2829705.67      10226153.1       2829787.5       10226215.
      2830205.66      10226503.1
#Sta/Elev= 30
  4897.4 1119.96  4940.1 1114.96  4954.6 1111.81  4960.9 1109.03  4969.2 1104.03
  4975.5 1097.71  4978.2 1096.29  4983.7 1093.39  4985.9 1090.23  4986.4 1089.73
  4993.6 1089.73  4994.1 1090.23  4995.7 1092.16  5019.6 1093.92  5025.6 1095.48
  5034.2  1096.6  5055.4 1097.51  5133.2  1098.9  5162.9 1098.74    5169 1098.18
  5198.8 1099.53  5213.7 1099.56  5219.7 1098.91    5335 1103.49    5350 1104.32
    5357 1103.79  5458.5  1105.4  5500.4 1106.88  5504.8 1108.14  5507.8 1108.14
#Mann= 5 ,-1 , 0
  4897.4     .05       0  4978.2     .12       0  4985.9     .07       0
  4994.1     .12       0    5335     .05       0
Bank Sta=4985.9,4994.1
XS Rating Curve= 0 ,0
Exp/Cntr=0.3,0.1

Type RM Length L Ch R = 1 ,6417    ,472,472,472
BEGIN DESCRIPTION:
LITTLE LLANO 027 14.0
END DESCRIPTION:
XS GIS Cut Line= 3
      2829555.71     10226303.15      2829748.75       10226630.
      2830155.66      10226803.1
#Sta/Elev= 30
  4620.4 1115.41  4643.3 1113.71  4665.3 1112.18  4678.4    1113  4692.5 1110.47
  4724.8 1108.36  4766.7 1105.81  4794.6 1102.02  4824.3 1101.01  4852.6 1095.61
  4905.2 1094.36  4920.8 1093.22  4926.6 1091.14  4933.9 1090.77  4942.3 1090.75
  4948.1  1092.8  4957.2 1092.77  4980.1 1090.43  4987.8 1088.07  4988.3 1087.57
  4996.1 1088.07  4998.9 1089.52  5007.5 1090.43  5029.3    1096  5069.6 1096.45
  5169.6 1102.28    5175 1101.75  5304.1 1106.79  5327.7 1106.79  5442.2 1112.97
#Mann= 7 ,-1 , 0
  4620.4     .05       0  4643.3     .12       0  4724.8     .05       0
  4824.3     .12       0  4980.1     .05       0  4987.8     .05       0
  4996.1     .05       0
Bank Sta=4987.8,4996.1
XS Rating Curve= 0 ,0
Exp/Cntr=0.3,0.1

Type RM Length L Ch R = 1 ,5945    ,475,475,475
BEGIN DESCRIPTION:
LITTLE LLANO 027 13.0
END DESCRIPTION:
XS GIS Cut Line= 3
      2829505.68     10226553.13      2829462.75       10226947.
      2829305.69     10227353.09
#Sta/Elev= 30
  4603.8 1102.27    4644 1100.36  4649.5 1099.47  4664.1 1099.56  4684.3 1097.44
  4784.2 1093.41  4955.9 1091.61  4991.3 1085.26  4991.8 1084.76  4999.8 1085.26
  5033.4  1091.7  5038.8 1091.18    5058  1092.2  5063.3 1091.43  5087.9 1093.56
  5093.3 1092.65  5117.9 1094.53  5124.5 1095.72  5142.5 1096.19  5147.8 1094.85
  5188.8  1097.7    5197 1099.47    5221 1101.39  5226.9 1102.59  5274.6 1106.21
  5281.5 1108.13  5286.8 1107.81    5306 1110.86  5395.9 1116.67  5435.4 1121.25
#Mann= 4 ,-1 , 0
  4603.8     .05       0  4784.2     .12       0  4991.3     .05       0
  4999.8     .05       0
Bank Sta=4991.3,4999.8
XS Rating Curve= 0 ,0
Exp/Cntr=0.3,0.1

Type RM Length L Ch R = 1 ,5470    ,253,253,253
BEGIN DESCRIPTION:
LITTLE LLANO 027 12.0
END DESCRIPTION:
XS GIS Cut Line= 3
      2829105.68     10226503.13      2829036.75       10226833.
       2828955.7     10227003.08
#Sta/Elev= 30
    4663 1102.53  4673.2 1101.91  4683.7 1100.27  4703.8 1098.15  4775.4 1093.99
  4795.8 1091.58  4877.5 1088.48  4882.8 1087.31  4887.9 1087.91    4898 1086.49
  4908.2 1086.07  4918.4 1084.18  4927.7 1084.42  4934.6 1082.37  4935.1 1081.87
  4942.6 1081.87  4943.1 1082.37    4949 1083.68  4989.9 1082.38  5002.8 1083.06
  5009.9 1084.26  5029.1 1084.82  5060.8  1087.1  5077.7 1089.25  5083.5  1090.9
  5099.8 1092.72  5106.2 1095.49  5111.8 1094.57  5128.9 1098.15  5188.4 1102.11
#Mann= 5 ,-1 , 0
    4663     .05       0  4683.7     .12       0  4934.6     .07       0
  4943.1     .12       0  5029.1     .05       0
Bank Sta=4934.6,4943.1
XS Rating Curve= 0 ,0
Exp/Cntr=0.3,0.1

Type RM Length L Ch R = 1 ,5217    ,692,692,692
BEGIN DESCRIPTION:
LITTLE LLANO 027 11.0
END DESCRIPTION:
XS GIS Cut Line= 3
      2829005.67     10226403.13      2828799.58     10226763.32
      2828728.53     10227078.74
#Sta/Elev= 30
  4698.7 1103.42  4728.2 1102.15  4773.3 1097.71  4814.5 1090.98  4836.9 1089.65
  4963.7 1086.77    4970  1081.6  4975.7 1078.35  4987.3 1077.88  4987.8 1077.38
  4995.8 1077.88  5007.4 1081.52  5021.3 1084.03  5072.2 1084.42  5116.1 1086.31
  5144.2 1088.09  5156.9 1089.62  5164.7  1091.5  5201.3 1093.79  5243.4 1096.71
    5257 1096.91  5286.6 1095.63  5291.8 1094.16    5298 1094.28  5318.5 1096.63
  5340.1 1097.03  5369.7 1099.87  5383.4 1099.91  5426.6 1104.24    5437 1104.36
#Mann= 5 ,-1 , 0
  4698.7     .12       0  4773.3     .05       0  4987.3     .07       0
  4995.8     .05       0  5201.3     .05       0
Bank Sta=4987.3,4995.8
XS Rating Curve= 0 ,0
Exp/Cntr=0.3,0.1

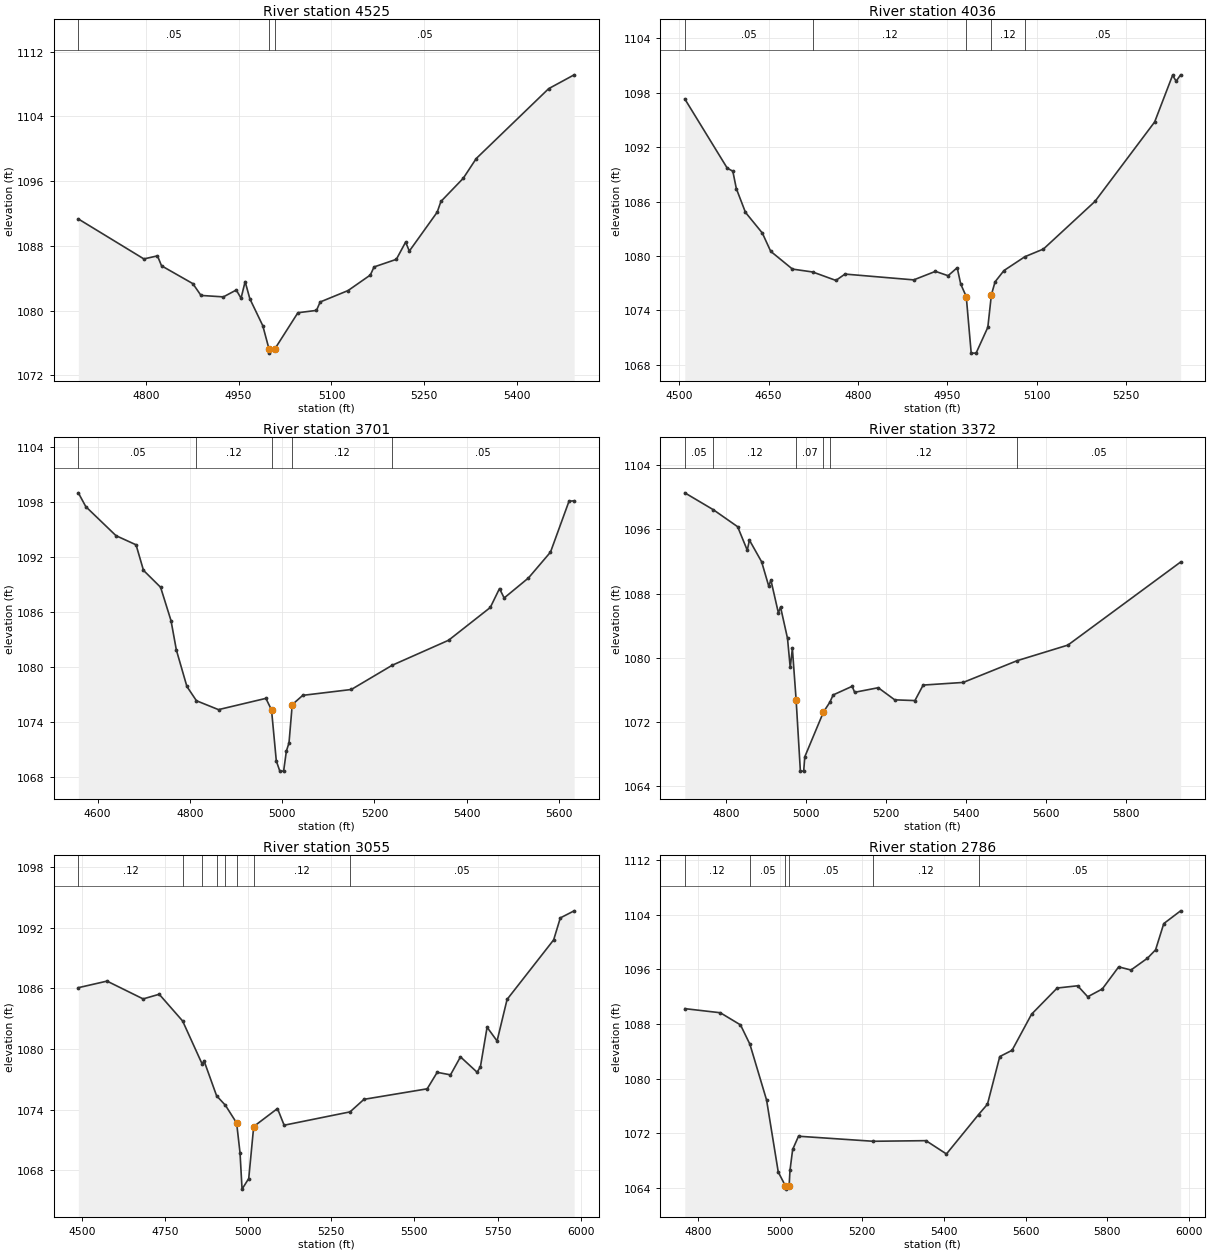
Type RM Length L Ch R = 1 ,4525    ,489,489,489
BEGIN DESCRIPTION:
LITTLE LLANO 027 10.0
END DESCRIPTION:
XS GIS Cut Line= 3
      2828055.66     10226453.08      2828257.25       10226687.
      2828531.45      10227095.5
#Sta/Elev= 30
  4691.2 1091.32  4797.1 1086.38    4819 1086.76  4825.6 1085.53  4876.1 1083.33
  4889.3 1081.87  4925.5 1081.69  4946.3 1082.54    4954 1081.52  4960.6 1083.58
  4968.2 1081.46  4989.1 1078.13  4999.2 1075.24  4999.7 1074.74  5008.4 1075.24
  5045.8 1079.73  5075.8 1080.02  5081.8 1081.06  5126.8 1082.47  5162.8 1084.39
  5168.8 1085.39  5204.8 1086.33  5219.8 1088.46  5225.8 1087.35  5270.8 1092.16
  5276.8 1093.48  5312.8 1096.34  5333.9 1098.79  5450.8 1107.42    5492 1109.13
#Mann= 3 ,-1 , 0
  4691.2     .05       0  4999.2     .03       0  5008.4     .05       0
Bank Sta=4999.2,5008.4
XS Rating Curve= 0 ,0
Exp/Cntr=0.3,0.1

Type RM Length L Ch R = 1 ,4036    ,335,335,335
BEGIN DESCRIPTION:
LITTLE LLANO 027 9.0
END DESCRIPTION:
XS GIS Cut Line= 3
      2827455.66     10226703.09       2827870.5       10226965.
      2828155.65     10227153.09
#Sta/Elev= 30
  4509.4 1097.33  4580.6  1089.7    4590 1089.36  4595.9 1087.44  4611.2 1084.82
  4639.5 1082.54  4653.6 1080.52  4690.1 1078.56  4724.1 1078.24    4763 1077.31
  4778.3 1078.01  4893.6 1077.37  4930.1 1078.31  4951.3 1077.83  4966.6 1078.71
  4972.5 1076.91  4981.8 1075.53  4990.1 1069.29  4998.3 1069.29    5018 1072.14
    5024 1075.73  5030.2 1077.16  5045.1  1078.4  5080.3 1079.93  5111.3 1080.77
  5197.9 1086.03    5298 1094.79  5328.1 1099.94  5334.1 1099.29  5341.6 1099.99
#Mann= 5 ,-1 , 0
  4509.4     .05       0  4724.1     .12       0  4981.8     .07       0
    5024     .12       0  5080.3     .05       0
Bank Sta=4981.8,5024
XS Rating Curve= 0 ,0
Exp/Cntr=0.3,0.1

Type RM Length L Ch R = 1 ,3701    ,329,329,329
BEGIN DESCRIPTION:
Mapping XS 5925a459
END DESCRIPTION:
XS GIS Cut Line= 3
      2827341.24     10226686.91      2827589.52     10227138.32
      2828146.82     10227186.93
#Sta/Elev= 30
  4558.3 1099.04  4574.5 1097.53  4639.9 1094.36  4683.4 1093.36  4699.5 1090.57
  4736.6 1088.72  4759.2 1085.07  4770.8 1081.86  4793.6 1077.88  4814.3 1076.32
  4862.1 1075.35  4964.8 1076.58    4977 1075.32  4987.4 1069.74    4995 1068.63
  5003.2 1068.63  5009.2 1070.82  5014.9 1071.72  5021.9  1075.9  5044.7 1076.91
  5149.9 1077.55  5238.6  1080.2  5360.7 1082.93  5451.1 1086.51  5471.1 1088.58
  5481.2 1087.55  5533.9 1089.74  5581.6 1092.56  5621.7 1098.12  5632.9 1098.17
#Mann= 5 ,-1 , 0
  4558.3     .05       0  4814.3     .12       0    4977     .07       0
  5021.9     .12       0  5238.6     .05       0
Bank Sta=4977,5021.9
XS Rating Curve= 0 ,0
Exp/Cntr=0.3,0.1

Type RM Length L Ch R = 1 ,3372    ,317,317,317
BEGIN DESCRIPTION:
LITTLE LLANO 027 8.0
END DESCRIPTION:
XS GIS Cut Line= 3
      2826957.54     10227028.93      2827426.32     10227218.18
      2828155.65     10227303.11
#Sta/Elev= 30
  4696.2 1100.56  4767.7 1098.45  4828.3 1096.34  4852.4 1093.41  4857.8 1094.67
  4888.3 1091.97  4906.1 1088.94  4911.5 1089.69  4930.2  1085.6  4935.6 1086.33
    4953 1082.44  4959.8  1078.8  4965.2 1081.17  4974.6 1074.74  4985.2 1065.89
  4993.5 1065.89  4996.2 1067.67    5043 1073.26  5059.1 1074.49  5067.1 1075.38
  5114.8 1076.46  5120.8 1075.71  5179.9 1076.28  5221.2 1074.77  5271.6 1074.68
  5292.2 1076.61  5392.4 1076.94  5527.2 1079.65  5654.1 1081.59    5936 1091.94
#Mann= 6 ,-1 , 0
  4696.2     .05       0  4767.7     .12       0  4974.6     .07       0
    5043     .05       0  5059.1     .12       0  5527.2     .05       0
Bank Sta=4974.6,5043
XS Rating Curve= 0 ,0
Exp/Cntr=0.3,0.1

Type RM Length L Ch R = 1 ,3055    ,269,269,269
BEGIN DESCRIPTION:
Mapping XS 053fd746
END DESCRIPTION:
XS GIS Cut Line= 3
      2826841.64     10227551.34      2827416.68     10227421.15
      2828317.32      10227410.3
#Sta/Elev= 30
  4489.9 1086.05  4576.1  1086.7  4684.7 1084.94    4733  1085.4  4803.3 1082.76
  4862.5 1078.47  4867.6 1078.83  4905.5 1075.36    4932 1074.42  4965.7 1072.67
  4975.9 1069.72    4982 1066.13  5002.1 1067.18    5017 1072.32  5088.5  1074.1
  5108.5 1072.45  5306.6 1073.77  5348.5 1075.01  5538.5 1076.05  5568.5 1077.68
  5608.5 1077.43  5638.5 1079.21  5688.5 1077.69  5698.5 1078.24  5718.5 1082.14
  5748.5 1080.78  5778.6 1084.89  5918.6 1090.78  5938.6 1092.95  5980.2 1093.65
#Mann= 8 ,-1 , 0
  4489.9     .12       0  4803.3     .05       0  4862.5     .12       0
  4905.5     .05       0    4932     .12       0  4965.7     .07       0
    5017     .12       0  5306.6     .05       0
Bank Sta=4965.7,5017
XS Rating Curve= 0 ,0
Exp/Cntr=0.3,0.1

Type RM Length L Ch R = 1 ,2786    ,613,613,613
BEGIN DESCRIPTION:
Mapping XS c942d559
END DESCRIPTION:
XS GIS Cut Line= 3
      2827313.48     10227803.24      2827599.93     10227563.66
      2828436.77     10227501.16
#Sta/Elev= 30
  4766.7 1090.26  4853.5 1089.66  4902.9 1087.88  4925.9 1085.05  4966.7 1076.87
  4995.3 1066.31  5012.6 1064.32  5013.1 1063.82  5021.9 1064.32  5023.9 1066.55
  5030.5 1069.63  5044.8 1071.57  5227.6 1070.83  5356.5 1070.92  5406.6 1068.97
  5485.2 1074.75  5506.9 1076.26    5537 1083.24  5567.1 1084.16  5614.8 1089.45
  5677.4 1093.28  5727.5 1093.61  5752.1    1092  5787.7 1093.14  5827.8 1096.38
  5857.9 1095.92    5898 1097.64    5918 1098.87  5938.1 1102.72  5979.3 1104.59
#Mann= 6 ,-1 , 0
  4766.7     .12       0  4925.9     .05       0  5012.6     .05       0
  5021.9     .05       0  5227.6     .12       0  5485.2     .05       0
Bank Sta=5012.6,5021.9
XS Rating Curve= 0 ,0
Exp/Cntr=0.3,0.1

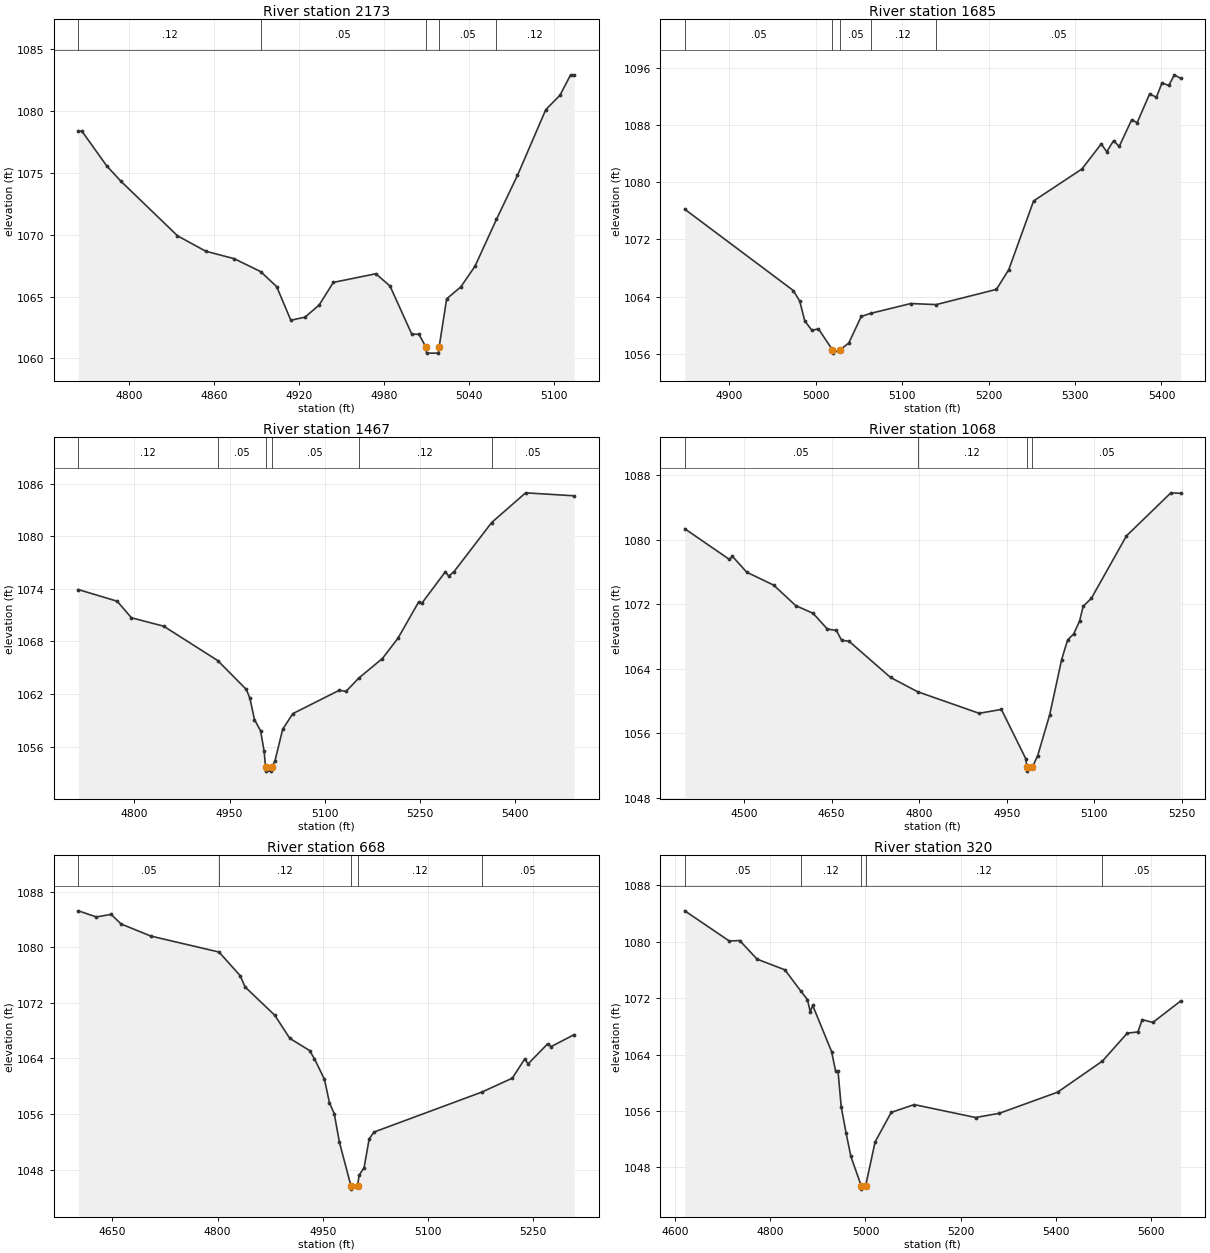
Type RM Length L Ch R = 1 ,2173    ,488,488,488
BEGIN DESCRIPTION:
LITTLE LLANO 027 5.0
END DESCRIPTION:
XS GIS Cut Line= 3
      2827655.71     10227953.11       2827891.5       10227951.
      2828005.68     10227953.11
#Sta/Elev= 30
  4764.2 1078.38  4766.7 1078.38  4784.2 1075.57  4794.2 1074.33  4834.2 1069.91
  4854.2 1068.66  4874.2 1068.06  4892.8 1067.02  4904.2  1065.8  4914.2 1063.08
  4924.2 1063.33  4934.2 1064.31  4944.2 1066.14  4974.2 1066.84  4984.2 1065.85
  4999.6 1061.95  5004.6 1061.95  5009.5 1060.92    5010 1060.42  5018.4 1060.42
  5018.9 1060.92  5024.2 1064.81  5034.2 1065.78  5044.2 1067.45  5059.3 1071.23
  5074.2  1074.8  5094.2 1080.12  5104.2 1081.28  5111.7 1082.93  5114.2 1082.93
#Mann= 5 ,-1 , 0
  4764.2     .12       0  4892.8     .05       0  5009.5     .05       0
  5018.9     .05       0  5059.3     .12       0
Bank Sta=5009.5,5018.9
XS Rating Curve= 0 ,0
Exp/Cntr=0.3,0.1

Type RM Length L Ch R = 1 ,1685    ,218,218,218
BEGIN DESCRIPTION:
LITTLE LLANO 027 4.0
END DESCRIPTION:
XS GIS Cut Line= 3
      2827505.66     10228153.07      2827578.75       10228286.
       2827905.7     10228553.13
#Sta/Elev= 30
  4848.3 1076.22  4973.9 1064.85  4981.4 1063.36  4987.1 1060.61  4995.5 1059.27
  5002.9  1059.5    5019 1056.59  5019.5 1056.09  5028.4 1056.59  5038.1  1057.5
  5052.5 1061.22  5063.3 1061.65  5109.9 1063.03  5139.2 1062.88    5209 1065.01
  5223.3 1067.78    5252 1077.38    5308 1081.86  5330.3 1085.36  5336.7 1084.27
  5344.6 1085.81  5351.1 1085.01  5365.5 1088.73  5371.9 1088.34  5386.3 1092.35
  5394.2  1091.9  5400.6 1093.89  5408.5 1093.54    5415 1095.03  5422.2 1094.53
#Mann= 5 ,-1 , 0
  4848.3     .05       0    5019     .05       0  5028.4     .05       0
  5063.3     .12       0  5139.2     .05       0
Bank Sta=5019,5028.4
XS Rating Curve= 0 ,0
Exp/Cntr=0.3,0.1

Type RM Length L Ch R = 1 ,1467    ,399,399,399
BEGIN DESCRIPTION:
LITTLE LLANO 027 3.0
END DESCRIPTION:
XS GIS Cut Line= 3
      2827284.16     10228162.85      2827502.94     10228616.95
      2827567.29     10228887.24
#Sta/Elev= 30
  4711.5 1073.91  4772.7 1072.58  4795.3 1070.69  4846.1 1069.73  4931.3 1065.81
  4976.3 1062.52  4981.9 1061.55  4989.3 1059.07  4998.9 1057.79  5004.5 1055.46
  5006.7 1053.69  5007.2 1053.19  5015.7 1053.19  5016.2 1053.69  5021.5 1054.33
  5033.7 1057.96  5049.7 1059.75  5123.1 1062.42  5133.6 1062.29  5154.1 1063.83
    5191 1066.04  5215.6 1068.36  5248.3 1072.51  5253.4 1072.37  5290.4 1075.95
  5295.6 1075.43  5304.1 1075.97  5363.3 1081.56  5416.9 1084.95  5493.4 1084.61
#Mann= 6 ,-1 , 0
  4711.5     .12       0  4931.3     .05       0  5006.7     .05       0
  5016.2     .05       0  5154.1     .12       0  5363.3     .05       0
Bank Sta=5006.7,5016.2
XS Rating Curve= 0 ,0
Exp/Cntr=0.3,0.1

Type RM Length L Ch R = 1 ,1068    ,400,400,400
BEGIN DESCRIPTION:
Mapping XS b3ba58e1
END DESCRIPTION:
XS GIS Cut Line= 4
      2827260.26     10228021.27      2827111.34       10228400.
      2827050.67     10228670.26      2827039.64     10228835.75
#Sta/Elev= 30
  4398.4 1081.37  4474.7 1077.57  4480.1 1077.94  4504.5 1075.98  4550.8 1074.37
  4588.5 1071.83  4618.3 1070.87  4642.7 1068.92  4658.3 1068.74  4667.1 1067.52
  4679.8 1067.41    4751 1062.91  4797.3 1061.14  4902.8 1058.46    4941 1058.94
  4982.8 1052.82  4984.7 1051.78  4985.2 1051.28  4994.2 1051.78  5003.3 1053.22
  5023.8 1058.28  5044.3 1065.13  5054.5 1067.57  5064.8  1068.3    5075 1069.91
  5081.2 1071.74  5095.2 1072.73  5155.4 1080.49  5231.5 1085.83  5248.2 1085.77
#Mann= 4 ,-1 , 0
  4398.4     .05       0  4797.3     .12       0  4984.7     .05       0
  4994.2     .05       0
Bank Sta=4984.7,4994.2
XS Rating Curve= 0 ,0
Exp/Cntr=0.3,0.1

Type RM Length L Ch R = 1 ,668     ,348,348,348
BEGIN DESCRIPTION:
Mapping XS 86f37ba0
END DESCRIPTION:
XS GIS Cut Line= 3
      2827195.91     10227977.15      2826824.53     10228333.82
       2826880.9     10228517.46
#Sta/Elev= 30
  4601.5 1085.24  4627.2 1084.36  4648.3 1084.73  4662.4 1083.35  4704.9 1081.61
  4802.1 1079.31  4832.2 1075.92  4839.2  1074.3  4881.6 1070.22    4903  1066.9
  4931.3 1065.14  4938.2 1063.96  4952.4 1061.01  4959.6 1057.64  4966.5 1056.02
  4973.7 1051.99  4990.1 1045.71  4990.6 1045.21  4999.6 1045.71    5002 1047.23
    5009 1048.31  5016.2 1052.43  5023.1 1053.42  5176.9 1059.17  5220.3 1061.17
  5237.8  1063.9    5243 1063.24  5270.5 1066.09  5275.8 1065.72  5308.5 1067.43
#Mann= 5 ,-1 , 0
  4601.5     .05       0  4802.1     .12       0  4990.1     .07       0
  4999.6     .12       0  5176.9     .05       0
Bank Sta=4990.1,4999.6
XS Rating Curve= 0 ,0
Exp/Cntr=0.3,0.1

Type RM Length L Ch R = 1 ,320     ,182,182,182
BEGIN DESCRIPTION:
LITTLE LLANO 027 2.0
END DESCRIPTION:
XS GIS Cut Line= 3
      2826738.13     10227629.63      2826651.71     10228104.01
      2826905.69     10228603.12
#Sta/Elev= 30
  4620.3 1084.37  4713.9 1080.09  4735.7 1080.16  4772.3 1077.52  4830.7 1076.01
  4863.9 1073.02    4878  1071.8    4884 1070.07  4889.1 1070.97  4928.8 1064.43
  4937.3 1061.67  4942.4 1061.62  4949.1 1056.59  4959.3 1052.89  4969.4 1049.56
    4991 1045.43  4991.5 1044.93  5000.5 1045.43  5020.3 1051.62  5054.1  1055.8
  5102.5 1056.91  5231.5 1055.08  5281.6 1055.68  5403.9 1058.67  5498.2 1063.08
  5550.3 1067.03  5572.7 1067.21  5581.8 1068.95  5604.1 1068.55  5662.5 1071.59
#Mann= 5 ,-1 , 0
  4620.3     .05       0  4863.9     .12       0    4991     .07       0
  5000.5     .12       0  5498.2     .05       0
Bank Sta=4991,5000.5
XS Rating Curve= 0 ,0
Exp/Cntr=0.3,0.1