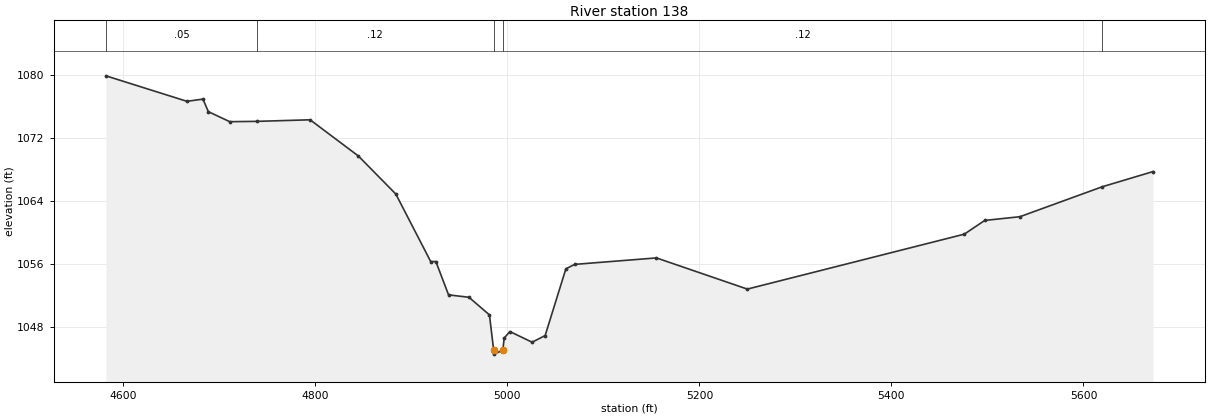
HEC-RAS study LITTLE LLANO 027.prj: LITTLE LLANO 027 Base Level Engineering

--- LITTLE LLANO 027.g01 (geometry) --- (continued)

Type RM Length L Ch R = 1 ,138     ,0,0,0
BEGIN DESCRIPTION:
LITTLE LLANO 027 1.0
END DESCRIPTION:
XS GIS Cut Line= 3
      2826607.58     10227640.73      2826453.15     10227947.73
      2826844.78      10228583.9
#Sta/Elev= 30
  4581.8 1079.84  4666.2 1076.61  4682.9 1076.89  4688.5  1075.3  4710.8 1074.03
  4739.1 1074.07  4794.5 1074.27  4844.7 1069.69  4883.8 1064.86  4920.1 1056.31
  4925.5 1056.31  4938.7 1052.09    4960 1051.78  4981.3 1049.55  4985.7 1045.08
  4986.2 1044.58  4995.2 1045.08  4996.7 1046.63  5002.6 1047.44  5025.7 1046.09
  5039.3 1046.93  5060.9 1055.39  5070.1 1055.95  5155.2 1056.77  5249.9 1052.82
  5475.9 1059.78  5497.2 1061.52  5533.8 1061.99  5619.7 1065.79  5672.5 1067.71
#Mann= 5 ,-1 , 0
  4581.8     .05       0  4739.1     .12       0  4985.7     .07       0
  4995.2     .12       0  5619.7     .05       0
Bank Sta=4985.7,4995.2
XS Rating Curve= 0 ,0
Exp/Cntr=0.3,0.1

Chan Stop Cuts=-1
Use User Specified Reach Order=0
Composite Channel Slope=5