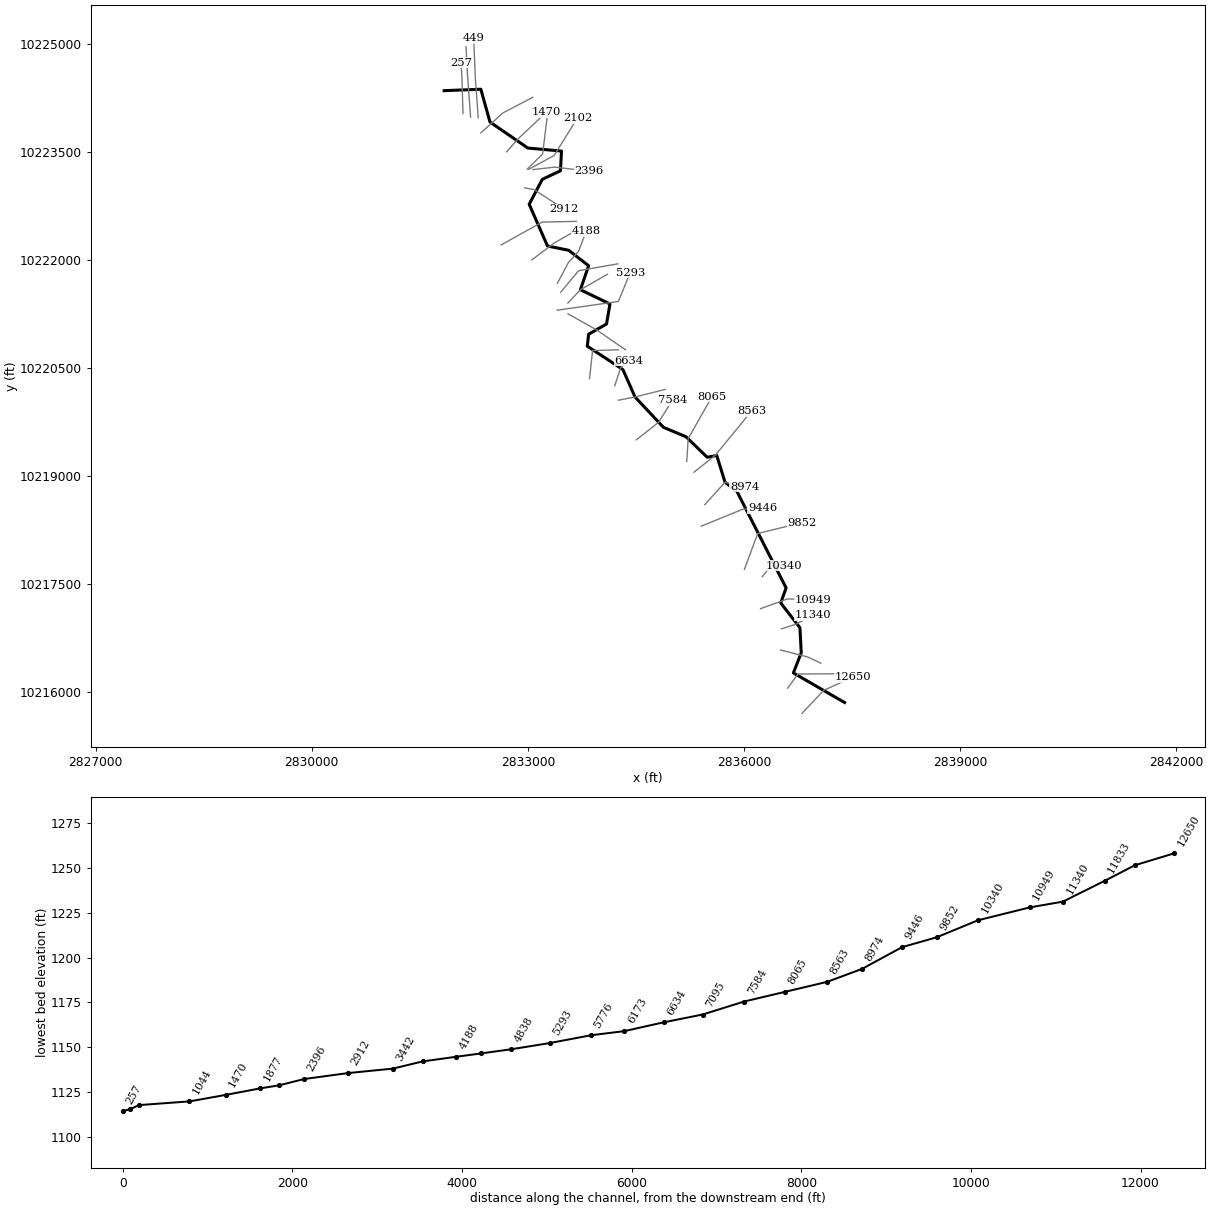
--- LITTLE LLANO 028.prj (project) ---

Proj Title=LITTLE LLANO 028 Base Level Engineering
Current Plan=p01
Default Exp/Contr=0.3,0.1
English Units
Geom File=g01
Flow File=f01
Plan File=p01
Y Axis Title=Elevation
X Axis Title(PF)=Main Channel Distance
X Axis Title(XS)=Station
BEGIN DESCRIPTION:
LITTLE LLANO 028
END DESCRIPTION:
DSS Export Rating Curves= 0
DSS Export Rating Curve Sorted= 0
DSS Export Volume Flow Curves= 0
DXF OffsetX= 0
DXF OffsetY= 0
DXF ScaleX= 1
DXF ScaleY= 10

--- LITTLE LLANO 028.p01 (plan) ---

Plan Title=Multiple Run
Short Identifier=Multiple
Geom File=g01
Flow File=f01
Subcritical Flow
K Sum by GR= 0
Std Step Tol= 0.01
Critical Tol= 0.01
Num of Std Step Trials= 20
Max Error Tol= 0.3
Flow Tol Ratio= 0.001
Split Flow NTrial= 30
Split Flow Tol= 0.02
Split Flow Ratio= 0.02
Log Output Level= 0
Friction Slope Method= 1
Unsteady Friction Slope Method= 2
Unsteady Bridges Friction Slope Method= 1
Parabolic Critical Depth
Global Vel Dist=  1 , 1 , 1
Global Log Level= 0
CheckData=True
Encroach Param= -1, 0, 0, 0
BEGIN DESCRIPTION:
Multiple Run
END DESCRIPTION:

--- LITTLE LLANO 028.f01 (steady flow) ---

Flow Title=Multiple
Number of Profiles=7
Profile Names=10-year,25-year,50-year,1pct_min,100-year,1pct_plu,500-year
River Rch & RM= LITTLE LLANO 028,Reach-1,12650
     441     714    1974    1666    2877    4967    4345
River Rch & RM= LITTLE LLANO 028,Reach-1,7095
     759    1277    3203    2492    4694    8842    6980
River Rch & RM= LITTLE LLANO 028,Reach-1,449
     807    1362    3450    2688    5067    9551    7527
Boundary for River Rch & Prof#=LITTLE LLANO 028,Reach-1,1
Up Type=0
Dn Type=3
Dn Slope=0.005
Boundary for River Rch & Prof#=LITTLE LLANO 028,Reach-1,2
Up Type=0
Dn Type=3
Dn Slope=0.005
Boundary for River Rch & Prof#=LITTLE LLANO 028,Reach-1,3
Up Type=0
Dn Type=3
Dn Slope=0.005
Boundary for River Rch & Prof#=LITTLE LLANO 028,Reach-1,4
Up Type=0
Dn Type=3
Dn Slope=0.005
Boundary for River Rch & Prof#=LITTLE LLANO 028,Reach-1,5
Up Type=0
Dn Type=3
Dn Slope=0.005
Boundary for River Rch & Prof#=LITTLE LLANO 028,Reach-1,6
Up Type=0
Dn Type=3
Dn Slope=0.005
Boundary for River Rch & Prof#=LITTLE LLANO 028,Reach-1,7
Up Type=0
Dn Type=3
Dn Slope=0.005

--- LITTLE LLANO 028.g01 (geometry) ---

Geom Title=Existing Conditions
Program Version=4.10

River Reach=LITTLE LLANO 028,Reach-1
Reach XY= 30
        2837396.       10215854.      2836685.25       10216265.
      2836794.75       10216545.      2836776.25       10216893.
      2836509.75       10217237.      2836584.25       10217446.
      2835900.75       10218788.      2835736.75       10218913.
      2835621.75       10219285.        2835489.       10219261.
        2835194.       10219546.      2834881.25       10219677.
      2834487.25       10220098.        2834319.       10220479.
       2833824.5       10220804.       2833843.5       10220970.
       2834091.5       10221112.      2834139.25       10221390.
      2833728.75       10221588.        2833843.       10221921.
       2833566.5       10222136.      2833272.25       10222195.
        2833018.       10222775.       2833199.5       10223121.
        2833452.       10223240.      2833466.75       10223514.
       2832999.5       10223556.        2832474.       10223917.
        2832347.       10224373.        2831837.       10224353.

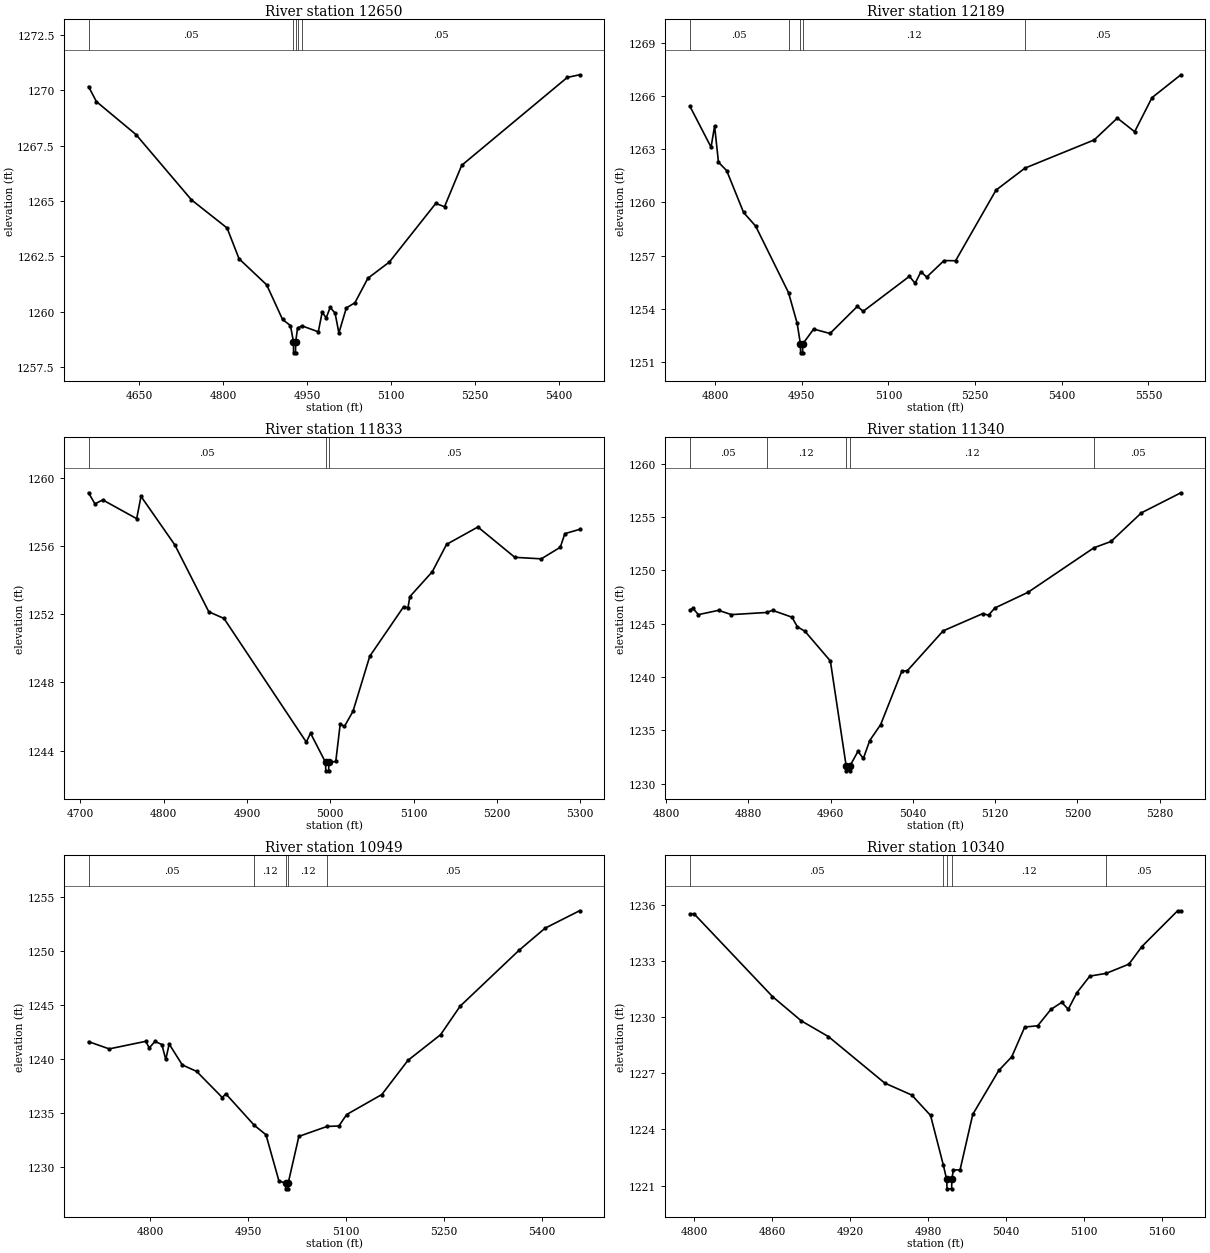
Type RM Length L Ch R = 1 ,12650   ,461,461,461
BEGIN DESCRIPTION:
LITTLE LLANO 028 27.0
END DESCRIPTION:
XS GIS Cut Line= 3
      2836805.65     10215703.08      2837107.25       10216024.
      2837505.65     10216203.09
#Sta/Elev= 30
  4559.6 1270.17  4573.6 1269.49  4644.4    1268  4743.5 1265.05  4807.1 1263.78
  4828.5 1262.39  4877.9 1261.21  4906.2 1259.65  4920.4 1259.37  4925.7 1258.64
  4925.9 1258.14  4929.4 1258.14  4929.7 1258.64    4933 1259.25  4940.8 1259.36
  4970.1 1259.09    4977 1259.97  4984.3 1259.72  4991.2 1260.19    5000 1259.94
  5006.9 1259.04  5020.2 1260.17  5035.5  1260.4  5058.7 1261.51    5097 1262.24
    5180 1264.89  5195.6 1264.74  5226.3 1266.61  5414.9 1270.58  5436.8  1270.7
#Mann= 5 ,-1 , 0
  4559.6     .05       0  4925.7     .05       0  4929.7     .05       0
    4933     .12       0  4940.8     .05       0
Bank Sta=4925.7,4929.7
XS Rating Curve= 0 ,0
Exp/Cntr=0.3,0.1

Type RM Length L Ch R = 1 ,12189   ,356,356,356
BEGIN DESCRIPTION:
LITTLE LLANO 028 26.0
END DESCRIPTION:
XS GIS Cut Line= 3
       2836605.7     10216053.13       2836749.5       10216250.
      2837355.69     10216253.11
#Sta/Elev= 30
  4756.2 1265.42  4792.9 1263.11    4799  1264.3  4805.7 1262.26  4819.9 1261.79
  4849.2 1259.43  4870.1 1258.66    4927 1254.91  4941.9 1253.19  4947.6 1252.02
  4947.9 1251.52  4951.4 1251.52  4951.6 1252.02  4970.5 1252.86  4998.8 1252.61
  5046.2 1254.14  5056.2 1253.86  5136.2 1255.83  5146.2 1255.44  5156.2 1256.09
  5166.2 1255.79  5196.2 1256.72  5216.2 1256.71  5286.2 1260.69  5336.3 1261.93
  5456.2 1263.52  5496.2 1264.75  5526.2 1263.98  5556.2  1265.9  5606.2 1267.19
#Mann= 5 ,-1 , 0
  4756.2     .05       0    4927     .12       0  4947.6     .07       0
  4951.6     .12       0  5336.3     .05       0
Bank Sta=4947.6,4951.6
XS Rating Curve= 0 ,0
Exp/Cntr=0.3,0.1

Type RM Length L Ch R = 1 ,11833   ,493,493,493
BEGIN DESCRIPTION:
LITTLE LLANO 028 25.0
END DESCRIPTION:
XS GIS Cut Line= 3
      2836508.22     10216583.42      2836882.75     10216487.04
      2837065.91     10216400.28
#Sta/Elev= 30
  4709.8 1259.14  4717.5 1258.49  4726.9 1258.72  4767.6 1257.62  4772.8 1258.93
  4813.5 1256.07  4854.2 1252.15  4872.4 1251.76  4971.2  1244.5  4976.3 1245.02
  4994.3 1243.31  4994.6 1242.81  4998.1 1242.81  4998.3 1243.31  5006.6 1243.36
  5011.9 1245.55    5017 1245.42  5027.3 1246.31  5047.4 1249.54  5088.1 1252.45
  5093.3 1252.39  5095.5 1253.04  5122.4  1254.5  5139.6 1256.11  5177.2 1257.13
  5221.5 1255.35  5253.3 1255.26  5276.1 1255.94  5281.6 1256.74  5299.2 1256.99
#Mann= 3 ,-1 , 0
  4709.8     .05       0  4994.3     .05       0  4998.3     .05       0
Bank Sta=4994.3,4998.3
XS Rating Curve= 0 ,0
Exp/Cntr=0.3,0.1

Type RM Length L Ch R = 1 ,11340   ,391,391,391
BEGIN DESCRIPTION:
LITTLE LLANO 028 24.0
END DESCRIPTION:
XS GIS Cut Line= 3
      2836519.15     10216876.75      2836720.25     10216941.48
      2836955.76     10217065.44
#Sta/Elev= 30
  4823.2 1246.29  4826.2 1246.43  4831.5 1245.85  4851.1 1246.25  4863.6 1245.85
  4897.8 1246.05  4903.6 1246.25  4922.5 1245.61  4927.7 1244.71  4935.1 1244.29
  4959.8 1241.51  4975.1 1231.72  4975.4 1231.22  4978.9 1231.22  4979.1 1231.72
  4986.6 1233.04  4991.9 1232.38  4998.1 1234.06  5008.7 1235.55  5029.4 1240.58
  5034.5 1240.58  5069.5 1244.33  5107.9 1245.94  5113.6  1245.8  5119.7 1246.47
    5152 1247.94  5216.1 1252.11  5232.7  1252.7  5262.2 1255.38  5300.6 1257.26
#Mann= 5 ,-1 , 0
  4823.2     .05       0  4897.8     .12       0  4975.1     .07       0
  4979.1     .12       0  5216.1     .05       0
Bank Sta=4975.1,4979.1
XS Rating Curve= 0 ,0
Exp/Cntr=0.3,0.1

Type RM Length L Ch R = 1 ,10949   ,609,609,609
BEGIN DESCRIPTION:
LITTLE LLANO 028 23.0
END DESCRIPTION:
XS GIS Cut Line= 3
      2836229.97     10217157.68       2836603.2     10217292.65
      2836958.48     10217283.01
#Sta/Elev= 30
  4705.5 1241.61  4737.2 1240.94  4793.2 1241.64  4798.5 1241.03  4807.3 1241.63
  4817.9 1241.34  4823.8 1239.96  4829.1 1241.39  4849.1 1239.46  4871.1 1238.86
  4910.5 1236.44  4915.8 1236.79  4959.4 1233.88  4977.4    1233  4997.1 1228.76
  5007.3  1228.5  5007.6    1228  5011.1    1228  5011.3  1228.5  5027.8 1232.85
    5071 1233.77  5089.1 1233.81    5101 1234.87  5154.9 1236.72  5194.9 1239.88
  5244.9 1242.25  5274.9 1244.89    5365 1250.05    5405  1252.1  5457.8 1253.71
#Mann= 5 ,-1 , 0
  4705.5     .05       0  4959.4     .12       0  5007.3     .07       0
  5011.3     .12       0    5071     .05       0
Bank Sta=5007.3,5011.3
XS Rating Curve= 0 ,0
Exp/Cntr=0.3,0.1

Type RM Length L Ch R = 1 ,10340   ,488,488,488
BEGIN DESCRIPTION:
LITTLE LLANO 028 22.0
END DESCRIPTION:
XS GIS Cut Line= 3
      2836255.68     10217603.11      2836381.25       10217763.
      2836555.67     10217753.11
#Sta/Elev= 30
  4796.7 1235.52  4799.9 1235.52  4860.3  1231.1  4882.5  1229.8  4903.4 1228.96
  4946.7 1226.48  4967.5 1225.84    4982 1224.75  4991.9 1222.08  4994.4 1221.33
  4994.7 1220.83  4998.2 1220.83  4998.4 1221.33  4999.5 1221.84  5004.7 1221.84
  5014.5 1224.81  5034.5 1227.15  5044.5 1227.88  5054.5 1229.47  5064.5 1229.54
  5074.6 1230.41    5083 1230.79    5088 1230.42  5094.6  1231.3  5104.6 1232.19
  5117.3 1232.34  5134.7 1232.83  5144.7 1233.77  5172.2 1235.68  5174.7 1235.68
#Mann= 5 ,-1 , 0
  4796.7     .05       0  4991.9     .12       0  4994.4     .07       0
  4998.4     .12       0  5117.3     .05       0
Bank Sta=4994.4,4998.4
XS Rating Curve= 0 ,0
Exp/Cntr=0.3,0.1

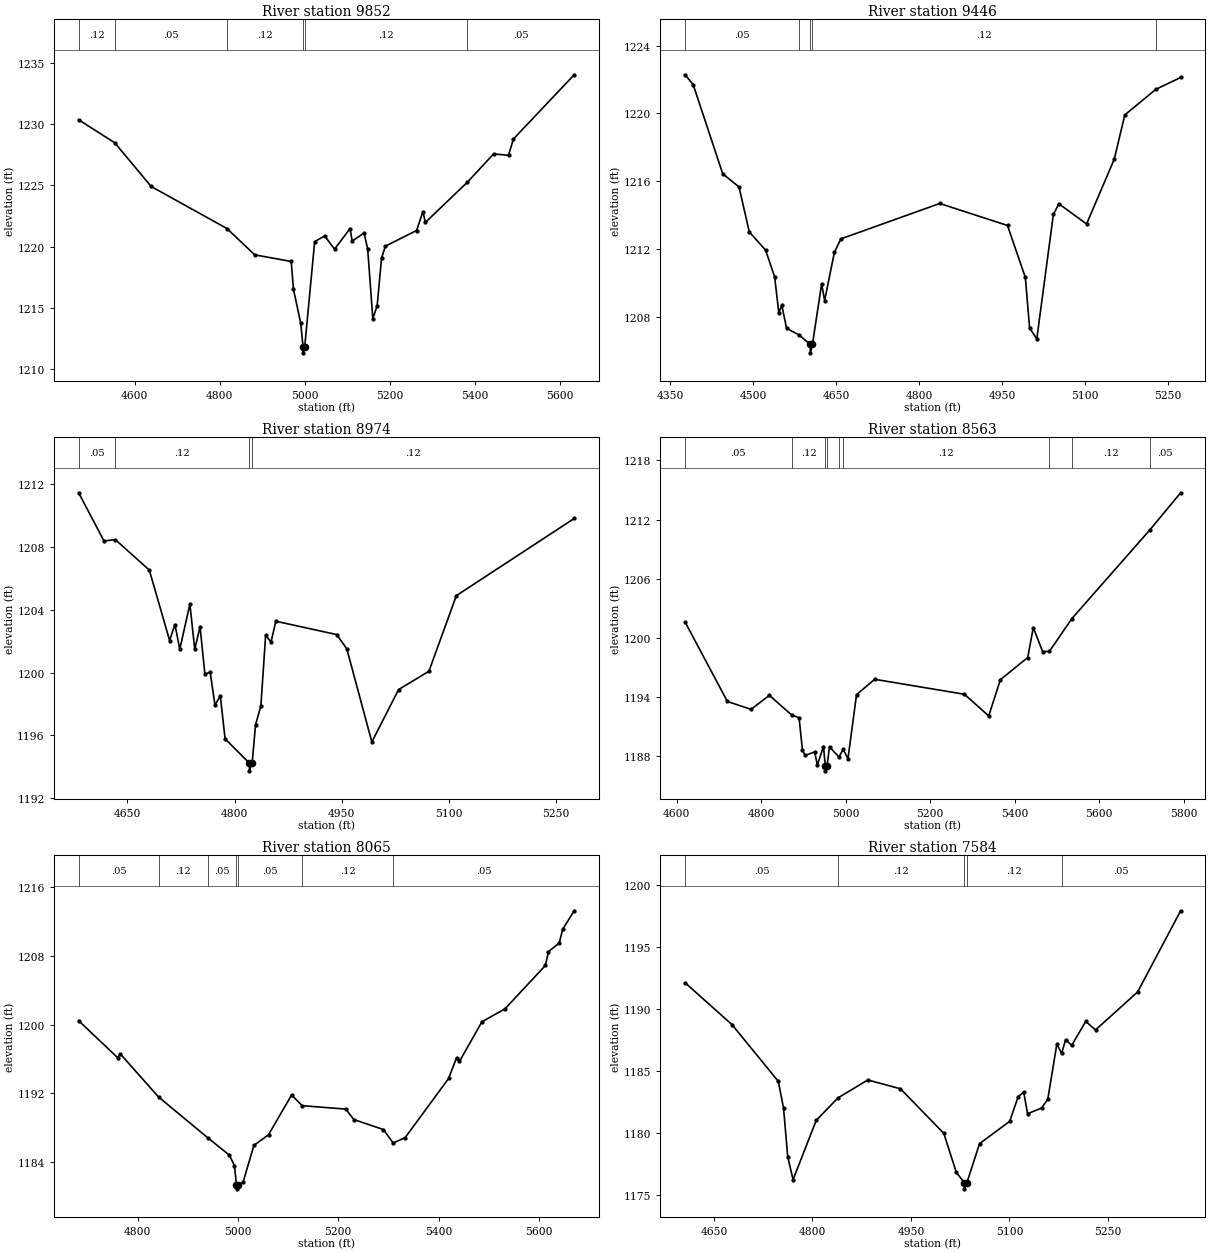
Type RM Length L Ch R = 1 ,9852    ,406,406,406
BEGIN DESCRIPTION:
LITTLE LLANO 028 21.0
END DESCRIPTION:
XS GIS Cut Line= 3
       2836005.7     10217703.14      2836190.25       10218202.
      2836805.67     10218353.11
#Sta/Elev= 30
  4468.1 1230.37  4553.1 1228.49  4638.7 1224.92  4817.1 1221.48  4882.3 1219.33
  4968.1 1218.79  4973.5  1216.5  4990.5 1213.75  4995.9 1211.82  4996.2 1211.32
  4999.9 1211.82  5023.3 1220.41  5046.8 1220.88    5070 1219.79  5106.5 1221.48
  5111.6 1220.46  5139.5 1221.11    5148 1219.81  5160.1  1214.1  5170.3 1215.18
  5180.6 1219.06  5189.6 1220.04    5263 1221.32  5277.9 1222.86  5283.6 1221.98
  5382.6 1225.27  5444.1 1227.58  5479.3 1227.47  5490.8  1228.8  5633.7 1234.05
#Mann= 6 ,-1 , 0
  4468.1     .12       0  4553.1     .05       0  4817.1     .12       0
  4995.9     .07       0  4999.9     .12       0  5382.6     .05       0
Bank Sta=4995.9,4999.9
XS Rating Curve= 0 ,0
Exp/Cntr=0.3,0.1

Type RM Length L Ch R = 1 ,9446    ,472,472,472
BEGIN DESCRIPTION:
LITTLE LLANO 028 20.0
END DESCRIPTION:
XS GIS Cut Line= 3
       2835405.7     10218303.12      2835982.75       10218539.
      2836255.69     10218553.11
#Sta/Elev= 30
  4376.6 1222.28  4391.3 1221.69  4444.7 1216.43  4474.1 1215.66  4492.8    1213
  4522.2 1211.93  4538.6 1210.35  4546.2 1208.22  4551.6 1208.67  4560.2 1207.31
  4583.2 1206.91    4603 1206.36  4603.3 1205.86    4607 1206.36  4623.7 1209.93
  4629.1 1208.95  4646.7 1211.79  4658.5 1212.59  4837.4 1214.68    4960 1213.38
  4992.3 1210.31    5000 1207.33    5013 1206.68    5043 1214.03    5053 1214.66
  5103.1 1213.47  5153.1 1217.29  5172.3 1219.91  5228.4 1221.42  5273.3 1222.12
#Mann= 5 ,-1 , 0
  4376.6     .05       0  4583.2     .12       0    4603     .07       0
    4607     .12       0  5228.4     .05       0
Bank Sta=4603,4607
XS Rating Curve= 0 ,0
Exp/Cntr=0.3,0.1

Type RM Length L Ch R = 1 ,8974    ,411,411,411
BEGIN DESCRIPTION:
LITTLE LLANO 028 19.0
END DESCRIPTION:
XS GIS Cut Line= 3
      2835455.66     10218603.09      2835736.75       10218913.
      2836005.66     10218853.12
#Sta/Elev= 30
  4581.6 1211.46  4617.1 1208.39  4633.1 1208.47  4680.6 1206.53    4709 1202.04
  4716.5 1203.06  4723.2 1201.48  4737.4 1204.36  4744.2 1201.47  4751.6 1202.92
  4758.4  1199.9  4765.8 1200.02  4772.5 1197.92    4780 1198.51  4786.7 1195.77
  4820.6 1194.23  4820.8 1193.73  4824.6 1194.23  4829.3 1196.65  4836.8 1197.88
  4843.5 1202.39    4851 1201.94  4857.7 1203.27  4942.9 1202.42  4957.1 1201.51
  4992.2 1195.57  5029.6 1198.91  5072.1 1200.08  5110.5  1204.9  5275.5 1209.82
#Mann= 4 ,-1 , 0
  4581.6     .05       0  4633.1     .12       0  4820.6     .07       0
  4824.6     .12       0
Bank Sta=4820.6,4824.6
XS Rating Curve= 0 ,0
Exp/Cntr=0.3,0.1

Type RM Length L Ch R = 1 ,8563    ,498,498,498
BEGIN DESCRIPTION:
LITTLE LLANO 028 18.0
END DESCRIPTION:
XS GIS Cut Line= 3
      2835305.72     10219053.14      2835603.25       10219290.
       2836105.7     10219903.12
#Sta/Elev= 30
  4619.7  1201.6  4719.8 1193.54  4775.8 1192.74  4819.1 1194.16  4871.9 1192.17
  4889.5 1191.89  4897.5  1188.6  4903.9 1188.08  4926.4 1188.41  4932.8 1187.09
  4947.2 1188.97  4951.6    1187  4951.8  1186.5  4955.6    1187  4961.6 1188.93
  4983.8  1187.9    4994 1188.69  5005.2 1187.72  5025.5 1194.23  5068.5 1195.79
    5281 1194.27  5338.4 1192.07    5366 1195.75  5430.7    1198  5443.9 1201.04
  5466.1  1198.6    5482 1198.62  5535.2 1201.95  5720.4 1210.98  5792.7 1214.72
#Mann= 9 ,-1 , 0
  4619.7     .05       0  4871.9     .12       0  4951.6     .07       0
  4955.6     .12       0  4983.8     .05       0    4994     .12       0
    5482     .05       0  5535.2     .12       0  5720.4     .05       0
Bank Sta=4951.6,4955.6
XS Rating Curve= 0 ,0
Exp/Cntr=0.3,0.1

Type RM Length L Ch R = 1 ,8065    ,481,481,481
BEGIN DESCRIPTION:
LITTLE LLANO 028 17.0
END DESCRIPTION:
XS GIS Cut Line= 3
      2835205.68      10219203.1      2835225.25       10219520.
      2835555.67     10220103.09
#Sta/Elev= 30
  4682.5 1200.46  4760.6 1196.14  4765.7 1196.59  4841.8 1191.59  4940.5 1186.82
  4983.1 1184.82  4993.1 1183.59  4997.1 1181.41  4997.3 1180.91  5001.1 1181.41
  5010.2 1181.66  5031.8 1185.96    5061  1187.2  5106.9 1191.82  5128.1 1190.58
    5215 1190.18  5230.9 1188.97  5290.1  1187.8  5309.4 1186.24  5333.4 1186.87
  5419.9 1193.74  5435.8 1196.15  5441.5 1195.72  5486.3 1200.33  5532.3 1201.84
  5612.8 1206.88    5619 1208.49  5640.6  1209.5  5647.2 1211.08  5670.2 1213.24
#Mann= 7 ,-1 , 0
  4682.5     .05       0  4841.8     .12       0  4940.5     .05       0
  4997.1     .05       0  5001.1     .05       0  5128.1     .12       0
  5309.4     .05       0
Bank Sta=4997.1,5001.1
XS Rating Curve= 0 ,0
Exp/Cntr=0.3,0.1

Type RM Length L Ch R = 1 ,7584    ,489,489,489
BEGIN DESCRIPTION:
LITTLE LLANO 028 16.0
END DESCRIPTION:
XS GIS Cut Line= 3
      2834505.68     10219503.11        2834815.       10219747.
      2835005.66     10220053.07
#Sta/Elev= 30
  4606.1 1192.12  4677.5 1188.75    4748 1184.18    4756 1182.02  4762.4 1178.08
  4770.5 1176.26  4805.7 1181.03  4838.7 1182.84  4884.3 1184.29    4934 1183.58
    5000 1179.99    5019 1176.85  5031.2 1176.02  5031.4 1175.52  5035.2 1176.02
  5054.4 1179.16  5100.4 1180.96  5113.2 1182.95  5121.7  1183.3  5127.6 1181.57
  5148.8 1182.03  5158.3 1182.73  5172.1 1187.18  5179.4 1186.43  5185.4 1187.53
  5194.8 1187.08  5216.1 1189.01    5231 1188.32  5295.1 1191.38  5360.6 1197.92
#Mann= 5 ,-1 , 0
  4606.1     .05       0  4838.7     .12       0  5031.2     .07       0
  5035.2     .12       0  5179.4     .05       0
Bank Sta=5031.2,5035.2
XS Rating Curve= 0 ,0
Exp/Cntr=0.3,0.1

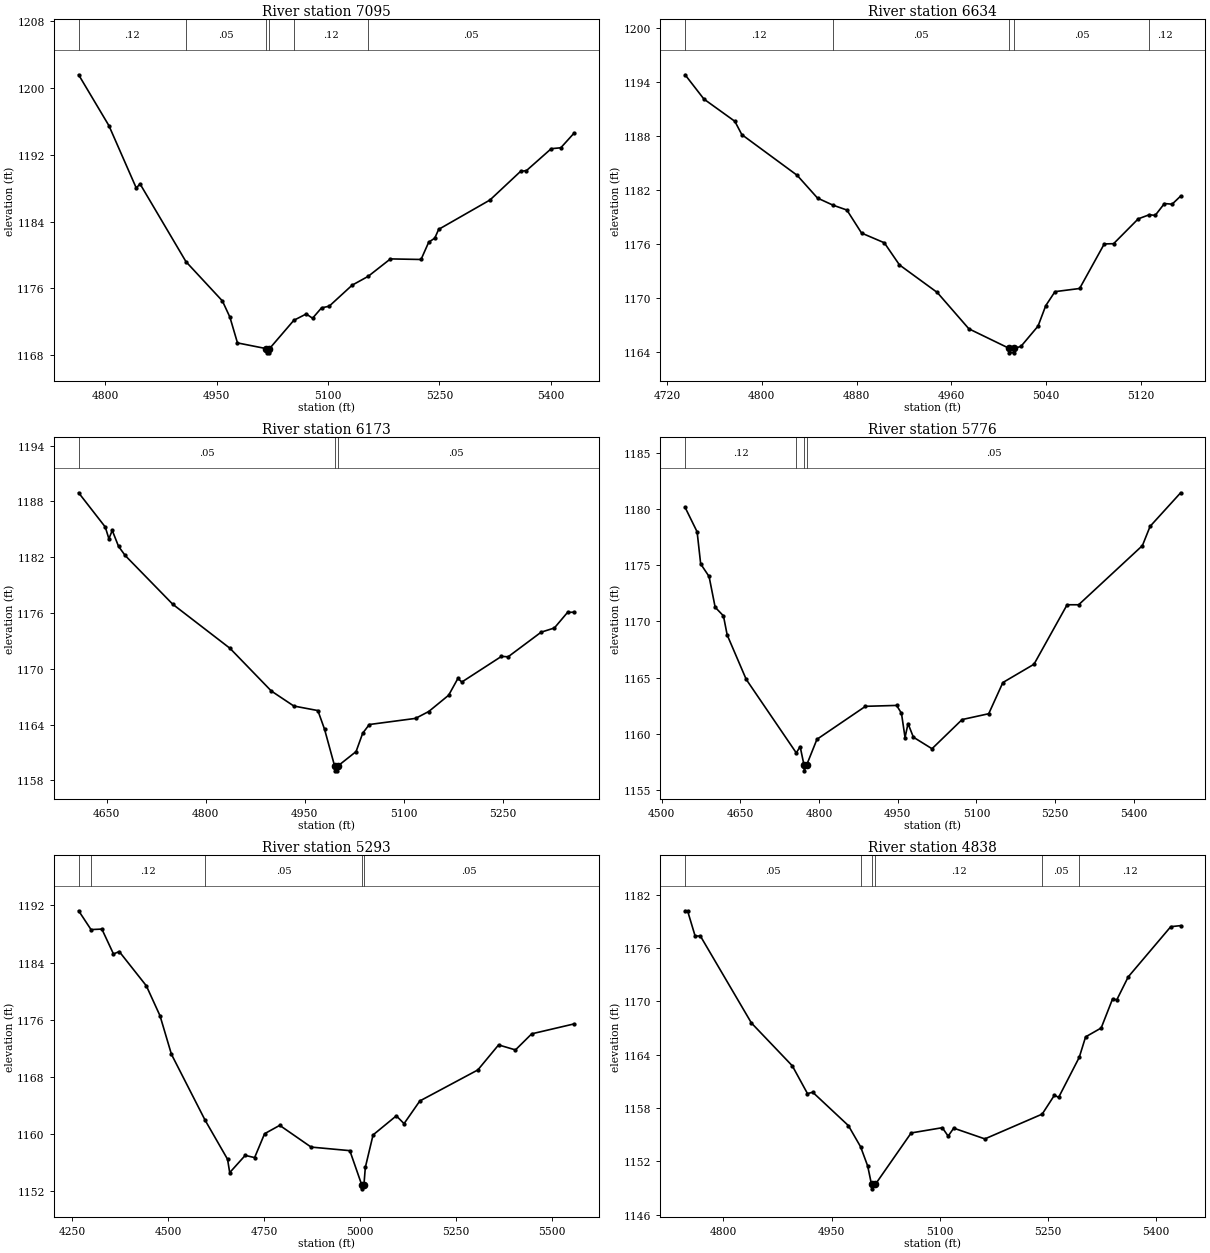
Type RM Length L Ch R = 1 ,7095    ,461,461,461
BEGIN DESCRIPTION:
LITTLE LLANO 028 15.0
END DESCRIPTION:
XS GIS Cut Line= 3
      2834255.66     10220053.11      2834487.25       10220098.
      2834905.65      10220203.1
#Sta/Elev= 30
  4764.1 1201.61  4804.9 1195.51  4841.7 1188.04  4846.8 1188.53  4908.7  1179.2
  4957.7  1174.5  4967.8 1172.56    4978 1169.47    5017 1168.78  5017.2 1168.28
  5020.8 1168.28  5021.1 1168.78  5053.9 1172.18  5070.6 1172.94  5079.1 1172.43
  5091.2 1173.67  5101.5 1173.87  5132.4 1176.39    5154 1177.45    5184 1179.54
  5225.2 1179.47  5235.5 1181.54  5243.7 1182.03  5248.9 1183.08    5318  1186.6
  5359.3 1190.04  5367.1 1190.12  5400.5 1192.75  5413.4 1192.86  5431.4 1194.63
#Mann= 6 ,-1 , 0
  4764.1     .12       0  4908.7     .05       0    5017     .05       0
  5021.1     .05       0  5053.9     .12       0    5154     .05       0
Bank Sta=5017,5021.1
XS Rating Curve= 0 ,0
Exp/Cntr=0.3,0.1

Type RM Length L Ch R = 1 ,6634    ,461,461,461
BEGIN DESCRIPTION:
LITTLE LLANO 028 14.0
END DESCRIPTION:
XS GIS Cut Line= 3
       2834205.7     10220253.15       2834287.5       10220505.
      2834405.68     10220603.11
#Sta/Elev= 30
  4735.2 1194.81  4751.1 1192.11  4777.2 1189.64  4783.1 1188.16  4829.8 1183.64
    4847 1181.11  4860.1 1180.32  4871.8 1179.78  4884.2 1177.22  4903.4 1176.14
  4916.2 1173.68  4948.1 1170.62  4974.8 1166.58  5008.8 1164.41  5009.1 1163.91
    5013 1163.91  5013.3 1164.41  5018.8 1164.63  5033.2 1166.88  5039.7 1169.15
  5047.5 1170.71  5068.3 1171.06  5089.1 1176.01    5097 1176.04  5117.8  1178.8
  5127.2 1179.26  5132.1 1179.18  5139.9  1180.5  5146.4 1180.43  5153.6 1181.33
#Mann= 5 ,-1 , 0
  4735.2     .12       0  4860.1     .05       0  5008.8     .05       0
  5013.3     .05       0  5127.2     .12       0
Bank Sta=5008.8,5013.3
XS Rating Curve= 0 ,0
Exp/Cntr=0.3,0.1

Type RM Length L Ch R = 1 ,6173    ,397,397,397
BEGIN DESCRIPTION:
LITTLE LLANO 028 13.0
END DESCRIPTION:
XS GIS Cut Line= 3
      2833855.68     10220353.09        2833898.       10220743.
      2834255.66     10220753.11
#Sta/Elev= 30
  4607.8 1188.92  4648.1 1185.24  4653.6 1183.98  4658.7 1184.87  4668.2 1183.16
  4678.2 1182.18  4750.3 1176.93  4836.8  1172.2  4899.5  1167.6  4933.5 1165.99
  4969.9  1165.5    4980 1163.49  4995.3 1159.52  4995.6 1159.02  4999.5 1159.02
  4999.8 1159.52  5027.7 1161.09  5037.7 1163.06  5047.7    1164  5117.7 1164.66
  5137.7  1165.4  5167.8 1167.15  5181.8 1168.95  5187.8 1168.57  5247.8 1171.33
  5257.8 1171.28  5307.8 1173.93  5327.8 1174.38  5347.8 1176.06  5357.8 1176.08
#Mann= 3 ,-1 , 0
  4607.8     .05       0  4995.3     .05       0  4999.8     .05       0
Bank Sta=4995.3,4999.8
XS Rating Curve= 0 ,0
Exp/Cntr=0.3,0.1

Type RM Length L Ch R = 1 ,5776    ,483,483,483
BEGIN DESCRIPTION:
LITTLE LLANO 028 12.0
END DESCRIPTION:
XS GIS Cut Line= 3
      2833555.67     10221253.12        2833953.       10221031.
      2834355.72     10220753.09
#Sta/Elev= 30
  4544.8 1180.17  4567.7 1177.99  4574.5 1175.13  4590.5 1174.01  4602.1 1171.27
  4617.9  1170.5    4625  1168.8  4661.3 1164.84  4756.7 1158.29  4764.1 1158.85
  4771.5 1157.19  4771.9 1156.69  4776.3 1157.19  4796.1  1159.5  4888.6 1162.44
    4948 1162.52  4957.2 1161.82    4964 1159.66  4969.7  1160.9  4979.9 1159.69
  5015.4 1158.66  5072.8 1161.26  5123.5 1161.78  5150.5 1164.56  5209.8 1166.19
  5272.9 1171.49  5294.9 1171.49  5416.4 1176.76  5431.1 1178.48  5489.3 1181.47
#Mann= 4 ,-1 , 0
  4544.8     .12       0  4756.7     .05       0  4771.5     .03       0
  4776.3     .05       0
Bank Sta=4771.5,4776.3
XS Rating Curve= 0 ,0
Exp/Cntr=0.3,0.1

Type RM Length L Ch R = 1 ,5293    ,455,455,455
BEGIN DESCRIPTION:
LITTLE LLANO 028 11.0
END DESCRIPTION:
XS GIS Cut Line= 3
      2833405.67     10221303.11       2834256.4     10221425.07
      2834420.48     10221825.52
#Sta/Elev= 30
  4266.9 1191.25  4299.2 1188.62  4327.5 1188.69  4357.8 1185.21  4372.8 1185.55
  4443.4 1180.76  4479.1 1176.57  4508.9 1171.18  4596.6 1161.97  4655.2  1156.5
  4660.9 1154.63  4701.3 1157.04  4725.8 1156.73  4751.8 1160.07  4791.3 1161.24
  4873.1  1158.2  4974.1  1157.7  5005.5 1152.86  5005.9 1152.36  5010.8 1152.86
  5014.5 1155.36  5034.7  1159.9  5095.3 1162.57  5115.5 1161.48  5156.6 1164.65
  5307.9 1168.99    5362 1172.49    5406 1171.79  5448.4 1174.04  5559.1 1175.43
#Mann= 5 ,-1 , 0
  4266.9     .05       0  4299.2     .12       0  4596.6     .05       0
  5005.5     .05       0  5010.8     .05       0
Bank Sta=5005.5,5010.8
XS Rating Curve= 0 ,0
Exp/Cntr=0.3,0.1

Type RM Length L Ch R = 1 ,4838    ,359,359,359
BEGIN DESCRIPTION:
LITTLE LLANO 028 10.0
END DESCRIPTION:
XS GIS Cut Line= 3
      2833555.72     10221403.15      2833728.75       10221588.
      2834105.69     10221803.11
#Sta/Elev= 30
  4746.8 1180.19  4750.2 1180.19  4760.7 1177.35    4768 1177.35  4838.8 1167.56
  4895.5 1162.74  4916.5 1159.62  4923.8 1159.77  4973.2 1156.02  4990.2 1153.63
    5000 1151.47  5005.3  1149.4  5005.7  1148.9  5010.6  1149.4  5060.3 1155.19
  5103.5 1155.78  5111.6 1154.83  5119.3 1155.73  5162.5 1154.52    5242 1157.31
    5259 1159.44  5264.8 1159.19  5293.4  1163.7  5302.2    1166  5323.8    1167
  5339.7 1170.29  5345.4 1170.16  5361.3 1172.75  5420.3  1178.4    5434 1178.52
#Mann= 6 ,-1 , 0
  4746.8     .05       0  4990.2     .12       0  5005.3     .07       0
  5010.6     .12       0    5242     .05       0  5293.4     .12       0
Bank Sta=5005.3,5010.6
XS Rating Curve= 0 ,0
Exp/Cntr=0.3,0.1

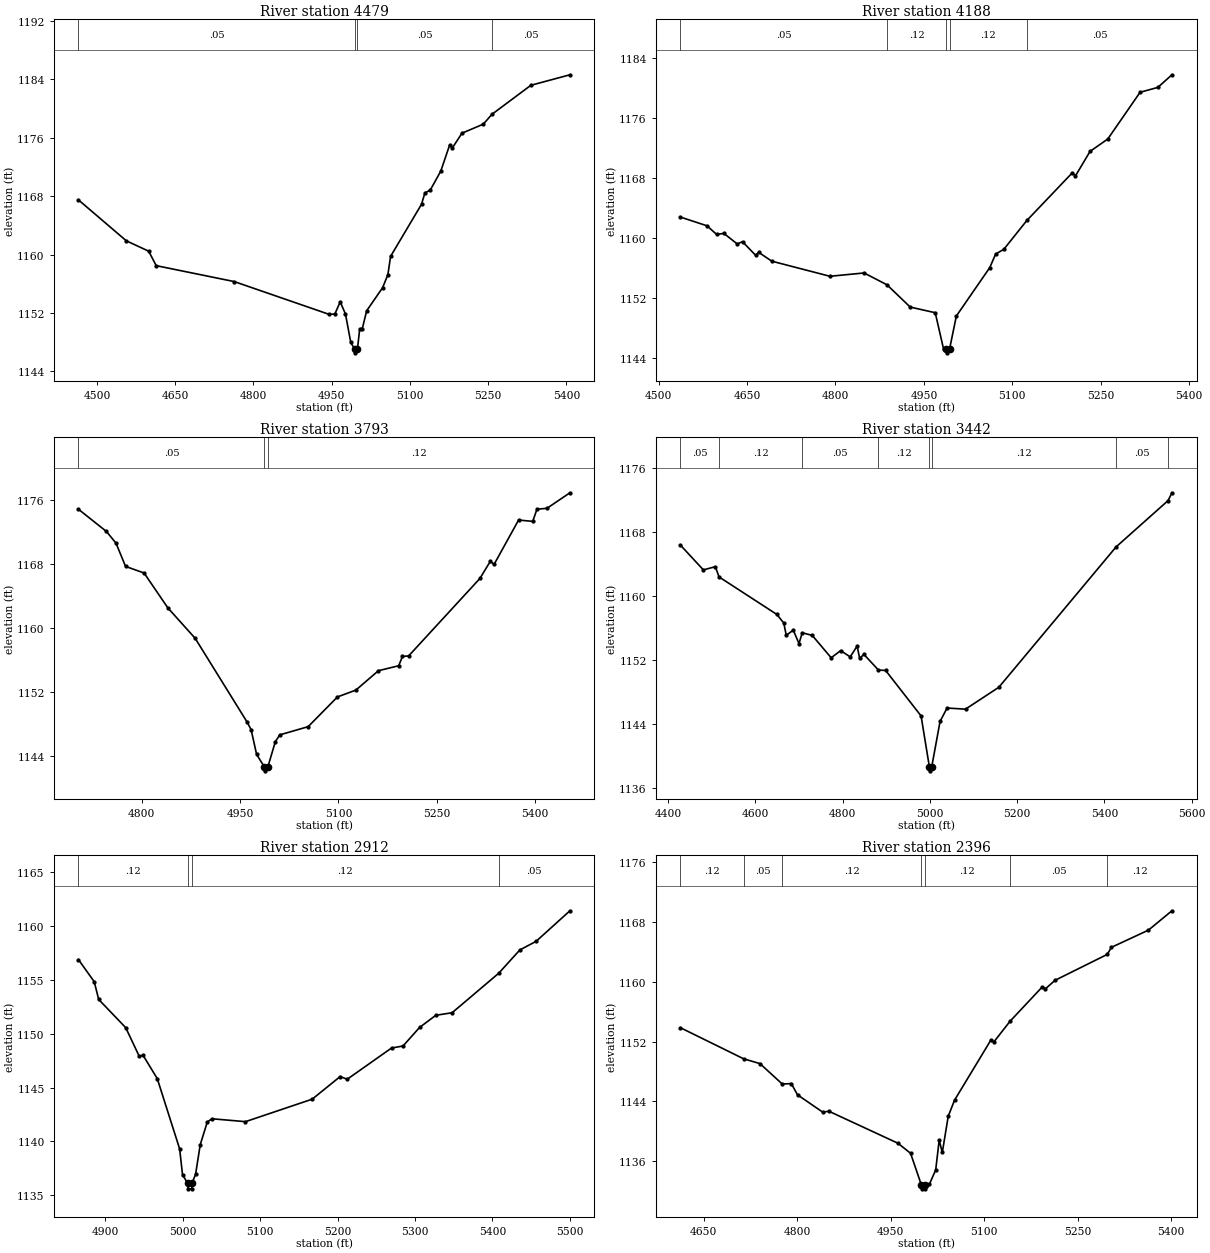
Type RM Length L Ch R = 1 ,4479    ,291,291,291
BEGIN DESCRIPTION:
LITTLE LLANO 028 9.0
END DESCRIPTION:
XS GIS Cut Line= 3
      2833455.71     10221553.14      2833703.33     10221851.43
      2834249.41     10221947.85
#Sta/Elev= 30
  4464.5 1167.48  4556.3 1161.88  4599.2 1160.46  4613.6 1158.48  4763.3  1156.3
  4944.5 1151.83  4956.1 1151.86  4966.3 1153.53  4976.4 1151.87  4986.6 1147.97
  4994.1 1147.05  4994.5 1146.55  4999.4 1147.05  5003.7 1149.84  5008.8 1149.88
    5017  1152.3  5047.5 1155.45  5057.7 1157.24  5062.9 1159.75  5122.2 1166.88
  5128.7 1168.44  5138.9 1168.81  5159.2 1171.43  5176.3 1175.03  5181.4  1174.6
  5199.8 1176.61  5240.6 1177.84  5257.4  1179.2  5331.8 1183.16  5406.7  1184.6
#Mann= 4 ,-1 , 0
  4464.5     .05       0  4994.1     .07       0  4999.4     .05       0
  5257.4     .05       0
Bank Sta=4994.1,4999.4
XS Rating Curve= 0 ,0
Exp/Cntr=0.3,0.1

Type RM Length L Ch R = 1 ,4188    ,395,395,395
BEGIN DESCRIPTION:
Mapping XS 971305d9
END DESCRIPTION:
XS GIS Cut Line= 4
      2833409.65     10221678.14      2833562.59     10221965.94
      2833703.02     10222120.27       2833809.5     10222399.59
#Sta/Elev= 30
  4537.1 1162.77  4582.1 1161.61  4598.5 1160.46  4610.7  1160.6  4633.3  1159.2
  4642.4 1159.49  4664.4  1157.7  4670.1 1158.06    4692  1156.9  4790.6 1154.89
  4848.5 1155.33  4887.3 1153.76  4926.8 1150.79  4969.2 1150.04  4983.3 1145.21
  4988.1  1145.2  4988.5  1144.7  4993.5  1145.2    5005  1149.6  5061.7 1156.05
  5071.7 1157.86  5085.4 1158.47  5124.6 1162.32  5201.6 1168.66    5207 1168.25
  5231.7 1171.51  5261.8 1173.16  5316.6 1179.38  5346.7 1180.03  5370.6 1181.71
#Mann= 5 ,-1 , 0
  4537.1     .05       0  4887.3     .12       0  4988.1     .07       0
  4993.5     .12       0  5124.6     .05       0
Bank Sta=4988.1,4993.5
XS Rating Curve= 0 ,0
Exp/Cntr=0.3,0.1

Type RM Length L Ch R = 1 ,3793    ,351,351,351
BEGIN DESCRIPTION:
LITTLE LLANO 028 8.0
END DESCRIPTION:
XS GIS Cut Line= 3
      2833055.66     10222003.09       2833372.1     10222241.24
      2833679.42     10222416.45
#Sta/Elev= 30
  4703.3 1174.84    4746 1172.06  4760.6  1170.6  4775.2 1167.69  4803.5 1166.86
  4839.7  1162.5  4881.4 1158.69  4960.5 1148.23  4966.8 1147.25  4975.1 1144.17
  4986.9 1142.61  4987.3 1142.11  4992.3 1142.61  5003.7 1145.76  5010.5 1146.61
  5053.8 1147.64  5098.5 1151.36  5126.5 1152.21    5161 1154.64  5191.9 1155.26
  5197.6 1156.42  5207.1 1156.49  5315.8 1166.18  5331.6 1168.32  5337.4 1167.94
  5374.8 1173.49  5396.4 1173.32  5402.8 1174.85    5418 1174.95  5453.1  1176.9
#Mann= 3 ,-1 , 0
  4703.3     .05       0  4986.9     .07       0  4992.3     .12       0
Bank Sta=4986.9,4992.3
XS Rating Curve= 0 ,0
Exp/Cntr=0.3,0.1

Type RM Length L Ch R = 1 ,3442    ,530,530,530
BEGIN DESCRIPTION:
LITTLE LLANO 028 7.0
END DESCRIPTION:
XS GIS Cut Line= 3
      2832628.26     10222210.66      2833199.35     10222527.73
      2833672.24     10222537.36
#Sta/Elev= 30
  4428.6 1166.35  4481.1 1163.25  4508.6 1163.65    4517 1162.37  4649.3 1157.68
  4665.4  1156.6  4671.1 1155.06  4687.1 1155.71  4700.2 1154.03  4707.8 1155.38
  4730.6 1155.05    4774 1152.25  4795.8 1153.15  4817.5 1152.36  4833.5 1153.71
  4839.3 1152.16  4848.9 1152.68  4882.2 1150.72  4898.8 1150.66    4980 1144.97
    4999  1138.6  4999.4  1138.1  5004.4  1138.6  5023.5 1144.29  5039.5 1145.96
  5081.8 1145.82  5158.2 1148.56  5426.9 1166.13  5545.9 1171.92  5554.8  1172.9
#Mann= 8 ,-1 , 0
  4428.6     .05       0    4517     .12       0  4707.8     .05       0
  4882.2     .12       0    4999     .07       0  5004.4     .12       0
  5426.9     .05       0  5545.9     .12       0
Bank Sta=4999,5004.4
XS Rating Curve= 0 ,0
Exp/Cntr=0.3,0.1

Type RM Length L Ch R = 1 ,2912    ,516,516,516
BEGIN DESCRIPTION:
LITTLE LLANO 028 6.0
END DESCRIPTION:
XS GIS Cut Line= 3
      2832955.66     10223003.12        2833088.       10222978.
      2833505.66     10222703.12
#Sta/Elev= 30
  4865.3 1156.89  4885.7 1154.83  4891.5 1153.18  4926.4 1150.56  4943.7 1147.92
  4948.8 1147.99  4967.1 1145.83    4996  1139.3  4999.7 1136.92  5006.4 1136.09
  5006.9 1135.59  5011.5 1135.59  5011.9 1136.09  5016.6 1136.95  5022.6 1139.69
  5031.7  1141.8  5037.7  1142.1    5081 1141.83  5167.2 1143.92  5203.3 1146.02
  5212.4 1145.77  5269.6 1148.67  5284.5 1148.86  5305.8 1150.58  5326.8 1151.71
  5347.9 1151.95  5408.1 1155.62  5435.3 1157.78  5456.3 1158.58    5500 1161.42
#Mann= 4 ,-1 , 0
  4865.3     .12       0  5006.4     .07       0  5011.9     .12       0
  5408.1     .05       0
Bank Sta=5006.4,5011.9
XS Rating Curve= 0 ,0
Exp/Cntr=0.3,0.1

Type RM Length L Ch R = 1 ,2396    ,294,294,294
BEGIN DESCRIPTION:
LITTLE LLANO 028 5.0
END DESCRIPTION:
XS GIS Cut Line= 3
      2833069.02     10223256.24      2833373.49       10223291.
      2833851.98     10223234.13
#Sta/Elev= 30
    4613 1153.85  4714.4 1149.69  4740.5 1149.05  4776.4 1146.31  4790.8 1146.38
  4800.8 1144.87  4841.1 1142.56  4851.2 1142.67  4961.9 1138.39  4982.1 1137.05
  4999.5 1132.79  4999.9 1132.29  5004.5 1132.29    5005 1132.79  5012.3 1132.91
  5022.4 1134.82    5028  1138.8    5033 1137.16  5042.5    1142  5052.6 1144.15
  5110.7 1152.17  5115.7 1151.95  5141.6 1154.71  5193.3 1159.31  5198.3 1159.05
  5213.7 1160.19  5297.5 1163.66  5304.3 1164.61  5363.6 1166.91  5401.3  1169.5
#Mann= 7 ,-1 , 0
    4613     .12       0  4714.4     .05       0  4776.4     .12       0
  4999.5     .07       0    5005     .12       0  5141.6     .05       0
  5297.5     .12       0
Bank Sta=4999.5,5005
XS Rating Curve= 0 ,0
Exp/Cntr=0.3,0.1

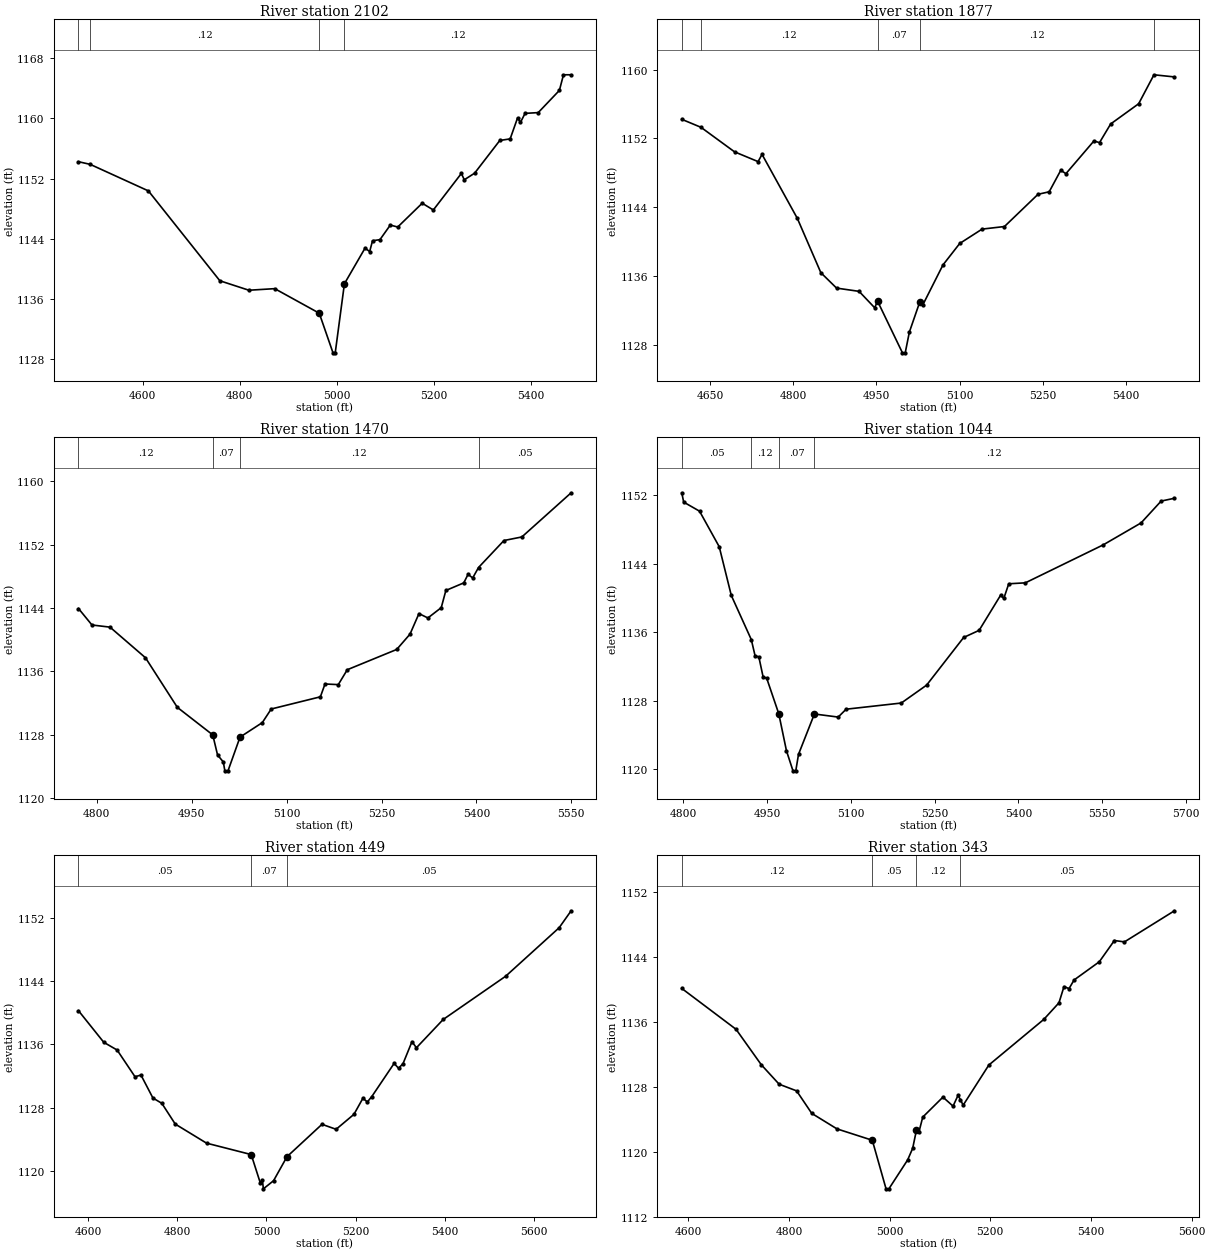
Type RM Length L Ch R = 1 ,2102    ,225,225,225
BEGIN DESCRIPTION:
Mapping XS 234fcda9
END DESCRIPTION:
XS GIS Cut Line= 3
      2833012.01     10223260.42      2833363.76     10223452.28
      2833687.71     10223973.66
#Sta/Elev= 30
  4467.8 1154.24  4491.8 1153.89  4611.8 1150.35  4758.9 1138.38  4818.7 1137.12
  4871.9 1137.33  4963.6 1134.06  4991.9 1128.78  4996.5 1128.78  5015.4 1137.98
  5057.9 1142.73  5067.4 1142.27  5073.3 1143.71  5088.6 1143.86  5109.9  1145.8
  5125.2 1145.54  5175.6 1148.71  5198.5 1147.81  5256.3 1152.68  5262.2 1151.83
  5283.5 1152.71  5335.4 1157.07  5356.7 1157.28    5372 1160.08  5377.9 1159.47
  5387.4 1160.68  5414.5 1160.78  5458.1 1163.74  5466.5 1165.82  5482.3 1165.82
#Mann= 4 ,-1 , 0
  4467.8     .05       0  4491.8     .12       0  4963.6     .07       0
  5015.4     .12       0
Bank Sta=4963.6,5015.4
XS Rating Curve= 0 ,0
Exp/Cntr=0.3,0.1

Type RM Length L Ch R = 1 ,1877    ,407,407,407
BEGIN DESCRIPTION:
LITTLE LLANO 028 4.0
END DESCRIPTION:
XS GIS Cut Line= 3
      2832991.15      10223263.2       2833204.4     10223472.87
      2833276.17     10224057.12
#Sta/Elev= 30
  4599.2 1154.22  4633.8 1153.29  4694.2 1150.44  4736.7  1149.3  4743.8 1150.14
  4807.4  1142.7  4849.8 1136.38  4878.1 1134.59  4918.7 1134.21  4946.8  1132.3
  4951.9 1133.08  4996.8 1127.06  5001.8 1127.06  5009.3 1129.48  5028.1 1132.99
  5033.2  1132.6  5069.8 1137.28    5100 1139.78  5140.3 1141.45  5180.6 1141.75
  5241.1  1145.5  5261.2 1145.79  5282.1 1148.29  5291.4  1147.9  5341.8  1151.7
  5351.9 1151.51    5372 1153.68  5422.4 1156.03    5450  1159.4  5486.9 1159.15
#Mann= 5 ,-1 , 0
  4599.2     .05       0  4633.8     .12       0  4951.9     .07       0
  5028.1     .12       0    5450     .05       0
Bank Sta=4951.9,5028.1
XS Rating Curve= 0 ,0
Exp/Cntr=0.3,0.1

Type RM Length L Ch R = 1 ,1470    ,426,426,426
BEGIN DESCRIPTION:
LITTLE LLANO 028 3.0
END DESCRIPTION:
XS GIS Cut Line= 3
      2832705.71     10223503.14      2832855.75       10223676.
      2833255.69     10224053.12
#Sta/Elev= 30
  4771.1 1143.92  4792.4 1141.84  4820.9 1141.57    4877  1137.7  4927.3 1131.44
  4983.3 1127.96  4990.9 1125.42    5000 1124.54  5002.4 1123.42  5007.4 1123.42
  5026.4 1127.68  5061.6 1129.51  5075.7 1131.23  5153.4 1132.77  5160.7 1134.39
  5181.7 1134.31  5195.9 1136.19    5274 1138.75    5295 1140.68  5309.2 1143.28
  5323.3 1142.73  5344.4 1144.03  5351.7  1146.2    5380 1147.16  5386.8 1148.24
  5394.1 1147.78  5403.3  1149.1  5443.5 1152.51  5471.8 1152.96  5549.7 1158.54
#Mann= 4 ,-1 , 0
  4771.1     .12       0  4983.3     .07       0  5026.4     .12       0
  5403.3     .05       0
Bank Sta=4983.3,5026.4
XS Rating Curve= 0 ,0
Exp/Cntr=0.3,0.1

Type RM Length L Ch R = 1 ,1044    ,595,595,595
BEGIN DESCRIPTION:
Mapping XS f1bc9dd6
END DESCRIPTION:
XS GIS Cut Line= 3
       2832346.9     10223766.91      2832653.61     10224044.29
      2833068.59     10224260.81
#Sta/Elev= 30
  4797.7 1152.29  4801.1  1151.2  4829.5 1150.14  4864.7 1145.99  4886.3  1140.3
  4922.1 1135.14  4928.9 1133.24  4935.6 1133.12  4943.1 1130.82  4949.8  1130.6
  4971.3 1126.47    4985 1122.16  4996.7 1119.81  5001.7 1119.81  5006.6 1121.74
    5035 1126.45  5077.6 1126.09  5091.8 1127.01  5190.5 1127.73  5235.8 1129.82
  5302.1 1135.39  5329.8 1136.22  5368.3 1140.33    5374 1139.96  5382.8 1141.66
  5412.5 1141.77    5552 1146.21  5619.6 1148.77  5655.5 1151.32  5679.3 1151.65
#Mann= 4 ,-1 , 0
  4797.7     .05       0  4922.1     .12       0  4971.3     .07       0
    5035     .12       0
Bank Sta=4971.3,5035
XS Rating Curve= 0 ,0
Exp/Cntr=0.3,0.1

Type RM Length L Ch R = 1 ,449     ,106,106,106
BEGIN DESCRIPTION:
LITTLE LLANO 028 2.0
END DESCRIPTION:
XS GIS Cut Line= 3
       2832310.8     10223976.61       2832270.2     10224531.45
      2832247.72     10225079.96
#Sta/Elev= 30
  4578.4 1140.24  4635.1 1136.25  4665.1 1135.27  4705.2  1131.9  4718.6 1132.11
  4745.4 1129.21  4765.4 1128.54  4795.5 1125.92  4865.7 1123.51  4965.9 1122.07
    4986 1118.54    4991 1118.85  4993.2 1117.74  5016.1 1118.77  5046.2  1121.8
  5124.7 1125.89  5156.4 1125.26  5196.4 1127.15  5216.5 1129.18  5226.5 1128.71
  5236.5  1129.4  5286.5 1133.58  5296.5 1132.97  5306.5 1133.55  5326.6 1136.33
  5336.6 1135.56  5396.6 1139.13  5536.7 1144.59  5656.8 1150.72  5683.7 1152.86
#Mann= 3 , 0 , 0
  4578.4     .05       0  4965.9     .07       0  5046.2     .05       0
Bank Sta=4965.9,5046.2
XS Rating Curve= 0 ,0
Exp/Cntr=0.3,0.1

Type RM Length L Ch R = 1 ,343     ,86,86,86
BEGIN DESCRIPTION:
Mapping XS 6d0feec9
END DESCRIPTION:
XS GIS Cut Line= 3
       2832204.8     10223985.64      2832159.69     10224603.62
      2832141.64     10224962.25
#Sta/Elev= 30
  4587.1 1140.08  4694.9 1135.05    4745 1130.69  4780.5 1128.29  4815.2 1127.47
  4845.3  1124.7  4895.4 1122.79  4965.6 1121.39  4992.9 1115.41  4998.5 1115.41
  5035.8 1118.97  5045.8  1120.4  5053.2 1122.62  5058.3 1122.43  5065.8 1124.24
  5105.9  1126.7    5126 1125.59    5136 1126.93  5140.4  1126.4  5146.1 1125.71
  5197.1 1130.65  5306.3 1136.27  5336.4 1138.31  5346.4 1140.31  5356.4 1140.06
  5366.4 1141.12  5416.5 1143.36  5446.5 1145.98  5466.5 1145.81  5565.8 1149.64
#Mann= 4 ,-1 , 0
  4587.1     .12       0  4965.6     .05       0  5053.2     .12       0
  5140.4     .05       0
Bank Sta=4965.6,5053.2
XS Rating Curve= 0 ,0
Exp/Cntr=0.3,0.1

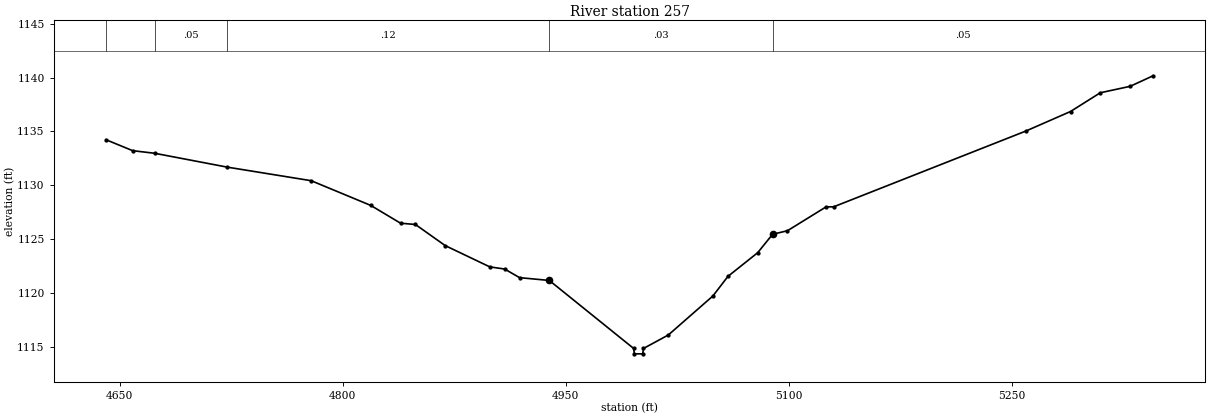
Type RM Length L Ch R = 1 ,257     ,0,0,0
BEGIN DESCRIPTION:
LITTLE LLANO 028 1.0
END DESCRIPTION:
XS GIS Cut Line= 3
      2832098.79     10224035.32      2832085.26     10224520.17
      2832071.76     10224738.51
#Sta/Elev= 30
    4641 1134.21  4658.8  1133.2  4673.5 1132.96  4722.4 1131.67  4778.8 1130.41
  4818.9 1128.11  4838.9 1126.46  4848.9 1126.34  4868.9 1124.38  4898.9  1122.4
  4908.9  1122.2  4918.9  1121.4  4938.9 1121.14  4995.6 1114.82  4996.1 1114.32
  5001.7 1114.32  5002.2 1114.82  5018.9 1116.07  5048.9  1119.7    5059 1121.52
    5079 1123.72    5089 1125.43    5099 1125.76    5125 1127.98    5130 1127.98
  5259.2 1135.02  5289.3 1136.84  5309.3 1138.58  5329.4 1139.18  5344.8 1140.16
#Mann= 5 ,-1 , 0
    4641     .12       0  4673.5     .05       0  4722.4     .12       0
  4938.9     .03       0    5089     .05       0
Bank Sta=4938.9,5089
XS Rating Curve= 0 ,0
Exp/Cntr=0.3,0.1

Chan Stop Cuts=-1
Use User Specified Reach Order=0
Composite Channel Slope=5