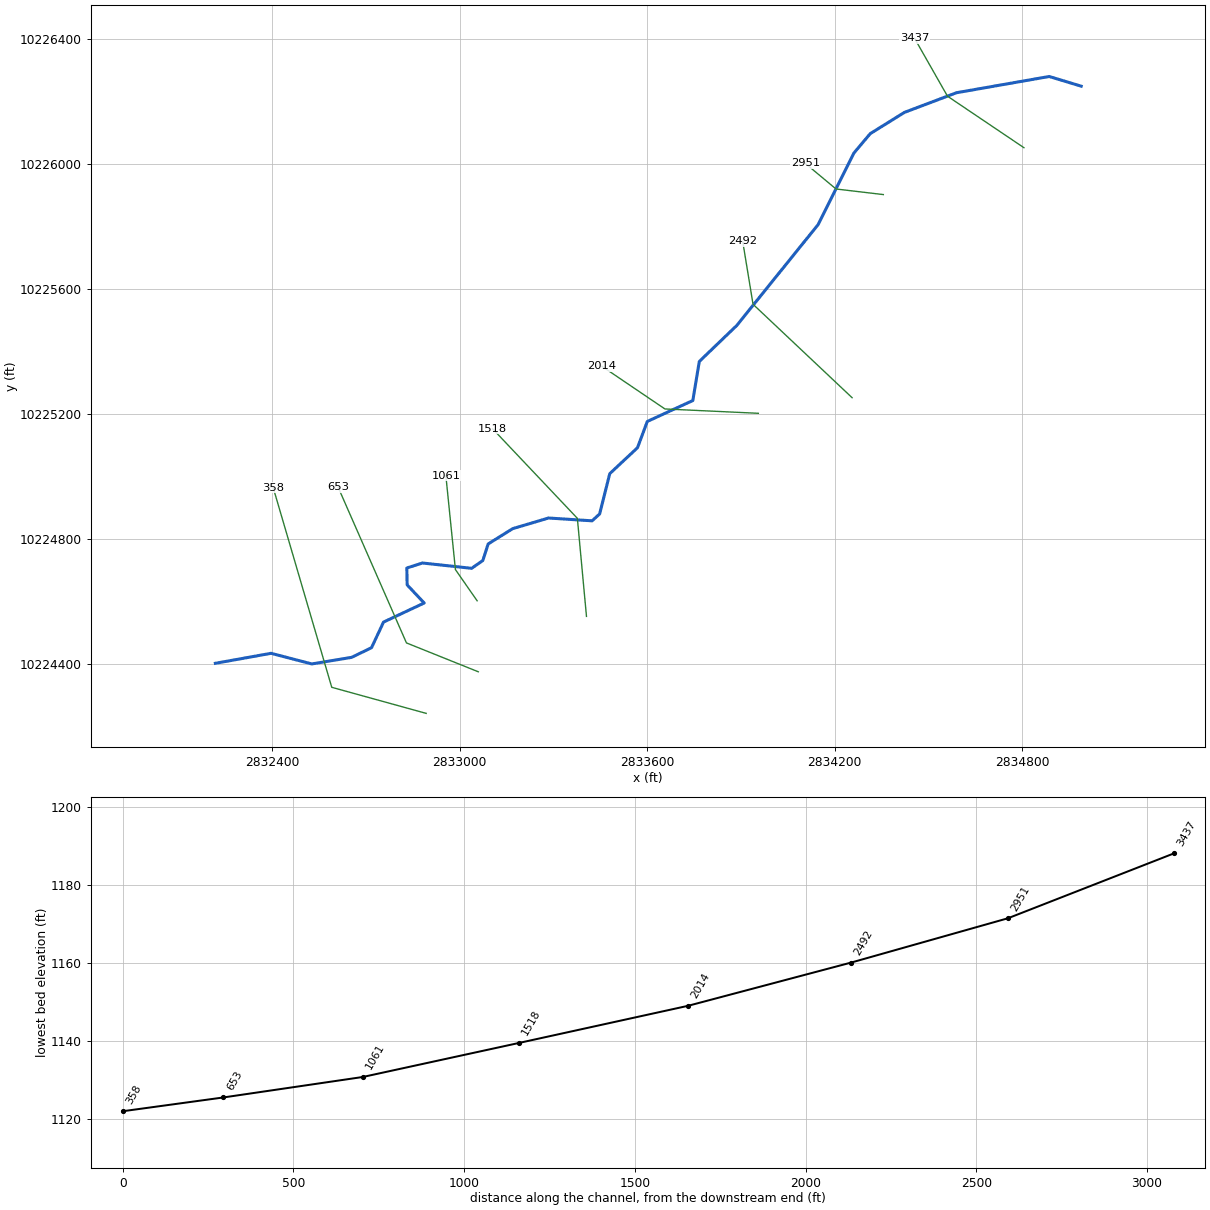
--- LITTLE LLANO 029.prj (project) ---

Proj Title=LITTLE LLANO 029 Base Level Engineering
Current Plan=p01
Default Exp/Contr=0.3,0.1
English Units
Geom File=g01
Flow File=f01
Plan File=p01
BEGIN DESCRIPTION:
LITTLE LLANO 029
END DESCRIPTION:

--- LITTLE LLANO 029.p01 (plan) ---

Plan Title=Multiple Run
Short Identifier=Multiple
Geom File=g01
Flow File=f01
Subcritical Flow
K Sum by GR= 0
Std Step Tol= 0.01
Critical Tol= 0.01
Num of Std Step Trials= 20
Max Error Tol= 0.3
Flow Tol Ratio= 0.001
Split Flow NTrial= 30
Split Flow Tol= 0.02
Split Flow Ratio= 0.02
Log Output Level= 0
Friction Slope Method= 1
Unsteady Friction Slope Method= 2
Unsteady Bridges Friction Slope Method= 1
Parabolic Critical Depth
Global Vel Dist=  1 , 1 , 1
Global Log Level= 0
CheckData=True
Encroach Param= -1, 0, 0, 0
BEGIN DESCRIPTION:
Multiple Run
END DESCRIPTION:

--- LITTLE LLANO 029.f01 (steady flow) ---

Flow Title=Multiple
Number of Profiles=7
Profile Names=10-year,25-year,50-year,1pct_min,100-year,1pct_plu,500-year
River Rch & RM= LITTLE LLANO 029,Reach-1,3437
     127     189     253     224     325     472     452
Boundary for River Rch & Prof#=LITTLE LLANO 029,Reach-1,1
Up Type=0
Dn Type=3
Dn Slope=0.005
Boundary for River Rch & Prof#=LITTLE LLANO 029,Reach-1,2
Up Type=0
Dn Type=3
Dn Slope=0.005
Boundary for River Rch & Prof#=LITTLE LLANO 029,Reach-1,3
Up Type=0
Dn Type=3
Dn Slope=0.005
Boundary for River Rch & Prof#=LITTLE LLANO 029,Reach-1,4
Up Type=0
Dn Type=3
Dn Slope=0.005
Boundary for River Rch & Prof#=LITTLE LLANO 029,Reach-1,5
Up Type=0
Dn Type=3
Dn Slope=0.005
Boundary for River Rch & Prof#=LITTLE LLANO 029,Reach-1,6
Up Type=0
Dn Type=3
Dn Slope=0.005
Boundary for River Rch & Prof#=LITTLE LLANO 029,Reach-1,7
Up Type=0
Dn Type=3
Dn Slope=0.005

--- LITTLE LLANO 029.g01 (geometry) ---

Geom Title=Existing Conditions

River Reach=LITTLE LLANO 029,Reach-1
Reach XY= 30
      2834989.00     10226250.00      2834886.50     10226281.00
      2834589.75     10226229.00      2834423.00     10226166.00
      2834313.75     10226098.00      2834261.50     10226036.00
      2834147.00     10225807.00      2833886.50     10225484.00
      2833766.75     10225369.00      2833746.00     10225244.00
      2833600.25     10225177.00      2833569.00     10225093.00
      2833480.25     10225010.00      2833447.75     10224881.00
      2833423.75     10224859.00      2833284.25     10224868.00
      2833169.75     10224834.00      2833091.00     10224785.00
      2833074.00     10224732.00      2833038.25     10224707.00
      2832880.75     10224724.00      2832830.75     10224708.00
      2832831.75     10224654.00      2832886.25     10224596.00
      2832756.25     10224535.00      2832717.75     10224453.00
      2832654.00     10224422.00      2832526.50     10224401.00
      2832396.25     10224435.00      2832218.00     10224403.00

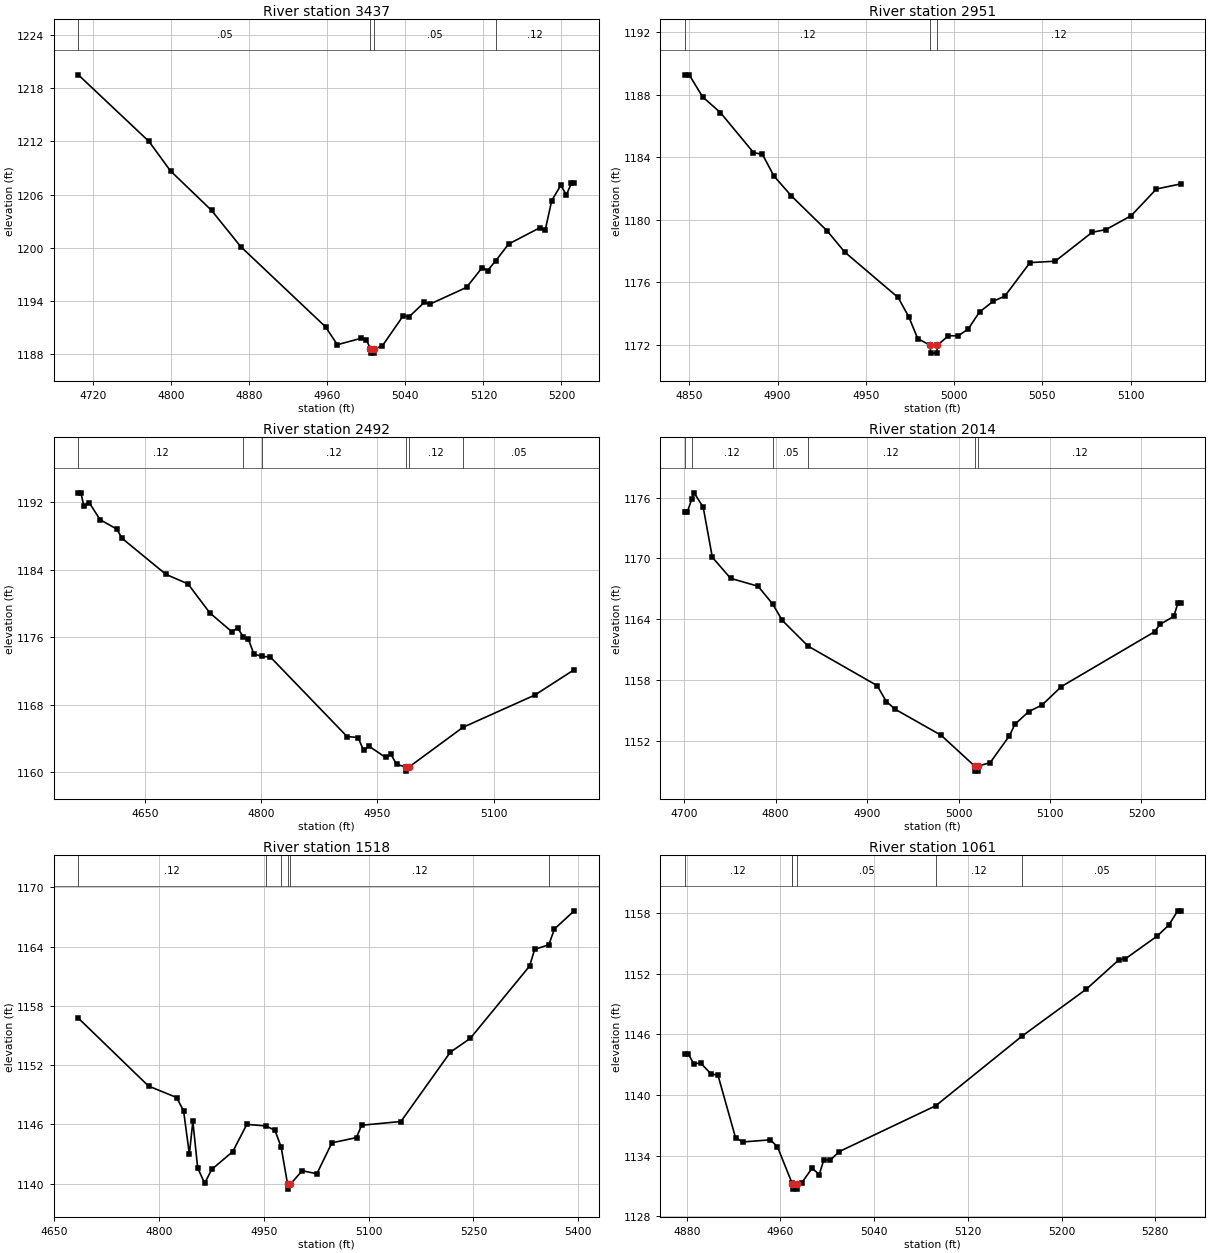
Type RM Length L Ch R = 1,3437,486,486,486
BEGIN DESCRIPTION:
LITTLE LLANO 029 7.0
END DESCRIPTION:
XS GIS Cut Line= 3
      2834805.72     10226053.09      2834561.00     10226218.00
      2834455.67     10226403.13
#Sta/Elev= 30
  4704.9 1219.52  4777.3 1212.00  4799.4 1208.67  4841.4 1204.22  4871.3 1200.13
  4958.2 1191.08  4970.3 1189.06  4994.2 1189.77  5000.0 1189.64  5004.1 1188.61
  5004.4 1188.11  5007.9 1188.11  5008.1 1188.61  5016.2 1188.89  5037.9 1192.34
  5043.6 1192.18  5059.5 1193.85  5065.2 1193.64  5102.7 1195.53  5118.6 1197.74
  5124.3 1197.43  5132.8 1198.56  5145.9 1200.43  5177.7 1202.25  5183.4 1202.01
  5190.0 1205.33  5199.3 1207.05  5205.0 1205.97  5210.1 1207.27  5213.0 1207.27
#Mann=4,-1,0
  4704.9    0.05       0  5004.1    0.05       0  5008.1    0.05       0
  5132.8    0.12       0
Bank Sta=5004.1,5008.1
Exp/Cntr=0.3,0.1

Type RM Length L Ch R = 1,2951,459,459,459
BEGIN DESCRIPTION:
LITTLE LLANO 029 6.0
END DESCRIPTION:
XS GIS Cut Line= 3
      2834355.70     10225903.11      2834204.25     10225921.00
      2834105.67     10226003.12
#Sta/Elev= 30
  4847.5 1189.26  4850.0 1189.26  4857.6 1187.85  4867.7 1186.84  4886.4 1184.29
  4891.5 1184.17  4897.9 1182.80  4907.9 1181.51  4928.1 1179.28  4938.1 1177.92
  4968.3 1175.02  4974.4 1173.77  4979.4 1172.39  4986.5 1171.96  4986.7 1171.46
  4990.2 1171.46  4990.5 1171.96  4996.8 1172.57  5002.3 1172.57  5007.9 1172.99
  5014.4 1174.09  5022.2 1174.78  5028.7 1175.10  5043.0 1177.25  5057.3 1177.34
  5078.2 1179.19  5086.0 1179.36  5100.3 1180.25  5114.6 1181.96  5128.3 1182.28
#Mann=3,-1,0
  4847.5    0.12       0  4986.5    0.07       0  4990.5    0.12       0
Bank Sta=4986.5,4990.5
Exp/Cntr=0.3,0.1

Type RM Length L Ch R = 1,2492,478,478,478
BEGIN DESCRIPTION:
LITTLE LLANO 029 5.0
END DESCRIPTION:
XS GIS Cut Line= 3
      2834255.66     10225253.14      2833938.75     10225552.00
      2833905.69     10225753.10
#Sta/Elev= 30
  4564.4 1193.13  4567.8 1193.13  4571.4 1191.59  4578.3 1191.98  4592.5 1189.94
  4613.9 1188.83  4620.8 1187.73  4677.4 1183.45  4705.8 1182.32  4734.1 1178.86
  4762.4 1176.64  4769.7 1177.08  4777.2 1176.05  4783.8 1175.73  4790.7 1174.01
  4801.1 1173.70  4811.8 1173.66  4910.9 1164.20  4925.0 1164.08  4932.3 1162.56
  4939.2 1163.05  4960.6 1161.72  4967.5 1162.10  4974.8 1160.88  4987.0 1160.59
  4987.2 1160.09  4991.0 1160.59  5060.4 1165.29  5153.1 1169.12  5203.8 1172.13
#Mann=6,-1,0
  4564.4    0.12       0  4777.2    0.05       0  4801.1    0.12       0
  4987.0    0.07       0  4991.0    0.12       0  5060.4    0.05       0
Bank Sta=4987,4991
Exp/Cntr=0.3,0.1

Type RM Length L Ch R = 1,2014,496,496,496
BEGIN DESCRIPTION:
LITTLE LLANO 029 4.0
END DESCRIPTION:
XS GIS Cut Line= 3
      2833955.73     10225203.11      2833656.75     10225217.00
      2833455.69     10225353.11
#Sta/Elev= 30
  4700.7 1174.54  4703.2 1174.54  4708.4 1175.87  4710.8 1176.48  4720.8 1175.07
  4730.8 1170.11  4750.8 1168.03  4780.8 1167.25  4796.9 1165.48  4807.2 1163.88
  4835.4 1161.34  4911.0 1157.43  4921.0 1155.86  4931.0 1155.08  4981.0 1152.52
  5017.6 1149.48  5017.9 1148.98  5021.4 1148.98  5021.6 1149.48  5034.6 1149.82
  5055.6 1152.47  5061.7 1153.62  5076.6 1154.85  5091.5 1155.53  5112.5 1157.34
  5214.3 1162.75  5220.4 1163.49  5235.3 1164.27  5239.8 1165.56  5242.8 1165.56
#Mann=6,-1,0
  4700.7    0.05       0  4708.4    0.12       0  4796.9    0.05       0
  4835.4    0.12       0  5017.6    0.07       0  5021.6    0.12       0
Bank Sta=5017.6,5021.6
Exp/Cntr=0.3,0.1

Type RM Length L Ch R = 1,1518,457,457,457
BEGIN DESCRIPTION:
LITTLE LLANO 029 3.0
END DESCRIPTION:
XS GIS Cut Line= 3
      2833405.68     10224553.15      2833376.50     10224867.00
      2833105.65     10225153.14
#Sta/Elev= 30
  4684.8 1156.75  4785.2 1149.87  4825.4 1148.71  4835.4 1147.34  4843.6 1142.98
  4848.6 1146.29  4855.5 1141.58  4865.5 1140.02  4875.6 1141.43  4905.7 1143.23
  4925.8 1145.99  4952.9 1145.83  4966.0 1145.40  4974.9 1143.69  4984.1 1139.93
  4984.3 1139.43  4988.1 1139.93  5005.0 1141.29  5026.0 1140.99  5047.5 1144.12
  5082.7 1144.65  5089.9 1145.90  5146.2 1146.28  5217.0 1153.31  5245.3 1154.69
  5330.2 1162.02  5337.5 1163.71  5357.8 1164.19  5365.8 1165.78  5394.0 1167.62
#Mann=6,-1,0
  4684.8    0.12       0  4952.9    0.05       0  4974.9    0.12       0
  4984.1    0.07       0  4988.1    0.12       0  5357.8    0.05       0
Bank Sta=4984.1,4988.1
Exp/Cntr=0.3,0.1

Type RM Length L Ch R = 1,1061,408,408,408
BEGIN DESCRIPTION:
LITTLE LLANO 029 2.0
END DESCRIPTION:
XS GIS Cut Line= 3
      2833055.71     10224603.07      2832986.25     10224703.00
      2832955.68     10225003.15
#Sta/Elev= 30
  4878.3 1144.04  4881.4 1144.04  4885.8 1143.10  4891.9 1143.15  4900.6 1142.10
  4906.7 1141.93  4921.6 1135.79  4927.7 1135.36  4951.3 1135.57  4957.4 1134.89
  4969.7 1131.34  4970.2 1131.20  4970.5 1130.70  4974.0 1130.70  4974.2 1131.20
  4978.3 1131.35  4987.0 1132.77  4993.1 1132.14  4997.0 1133.58  5002.6 1133.58
  5010.2 1134.41  5092.6 1138.94  5166.5 1145.84  5221.3 1150.47  5249.3 1153.39
  5254.4 1153.45  5281.6 1155.70  5291.6 1156.79  5299.2 1158.20  5301.7 1158.20
#Mann=6,-1,0
  4878.3    0.12       0  4969.7    0.05       0  4970.2    0.05       0
  4974.2    0.05       0  5092.6    0.12       0  5166.5    0.05       0
Bank Sta=4970.2,4974.2
Exp/Cntr=0.3,0.1

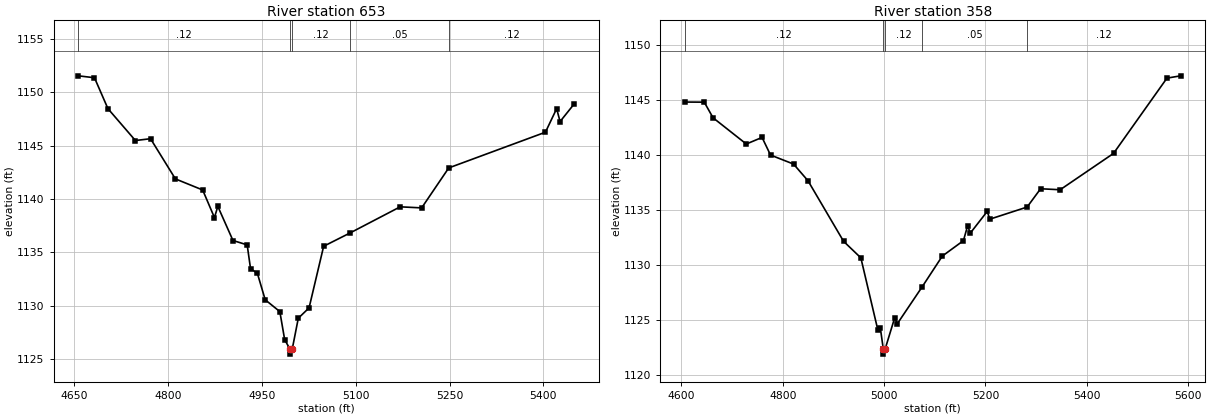
Type RM Length L Ch R = 1,653,295,295,295
BEGIN DESCRIPTION:
Mapping XS 9a2ad724
END DESCRIPTION:
XS GIS Cut Line= 3
      2833059.59     10224375.82      2832829.52     10224468.30
      2832610.75     10224966.74
#Sta/Elev= 30
  4656.8 1151.56  4682.6 1151.38  4704.1 1148.48  4748.0 1145.49  4772.2 1145.66
  4811.9 1141.89  4855.5 1140.85  4874.3 1138.26  4879.7 1139.31  4903.9 1136.11
  4926.6 1135.70  4932.0 1133.46  4942.8 1133.05  4955.4 1130.55  4978.8 1129.44
  4986.5 1126.81  4994.7 1125.95  4994.9 1125.45  4998.7 1125.95  5008.3 1128.82
  5025.5 1129.79  5048.8 1135.57  5091.4 1136.83  5171.1 1139.27  5205.4 1139.17
  5248.7 1142.92  5403.2 1146.27  5421.1 1148.48  5426.6 1147.27  5449.1 1148.92
#Mann=5,-1,0
  4656.8    0.12       0  4994.7    0.07       0  4998.7    0.12       0
  5091.4    0.05       0  5248.7    0.12       0
Bank Sta=4994.7,4998.7
Exp/Cntr=0.3,0.1

Type RM Length L Ch R = 1,358,0,0,0
BEGIN DESCRIPTION:
LITTLE LLANO 029 1.0
END DESCRIPTION:
XS GIS Cut Line= 3
      2832892.67     10224242.77      2832590.46     10224326.21
      2832403.25     10224964.51
#Sta/Elev= 30
  4606.6 1144.79  4645.0 1144.78  4662.4 1143.36  4728.0 1140.98  4759.1 1141.58
  4775.8 1139.98  4821.3 1139.16  4849.7 1137.65  4920.0 1132.15  4954.1 1130.65
  4987.5 1124.13  4992.7 1124.24  4998.3 1122.41  4998.5 1121.91  5002.3 1122.41
  5020.9 1125.21  5026.1 1124.67  5075.3 1128.03  5114.9 1130.81  5156.6 1132.21
  5164.9 1133.57  5170.1 1132.89  5203.5 1134.86  5208.7 1134.16  5282.3 1135.26
  5308.9 1136.92  5347.5 1136.83  5452.9 1140.13  5558.3 1146.96  5585.3 1147.17
#Mann=5,-1,0
  4606.6    0.12       0  4998.3    0.07       0  5002.3    0.12       0
  5075.3    0.05       0  5282.3    0.12       0
Bank Sta=4998.3,5002.3
Exp/Cntr=0.3,0.1

Chan Stop Cuts=-1