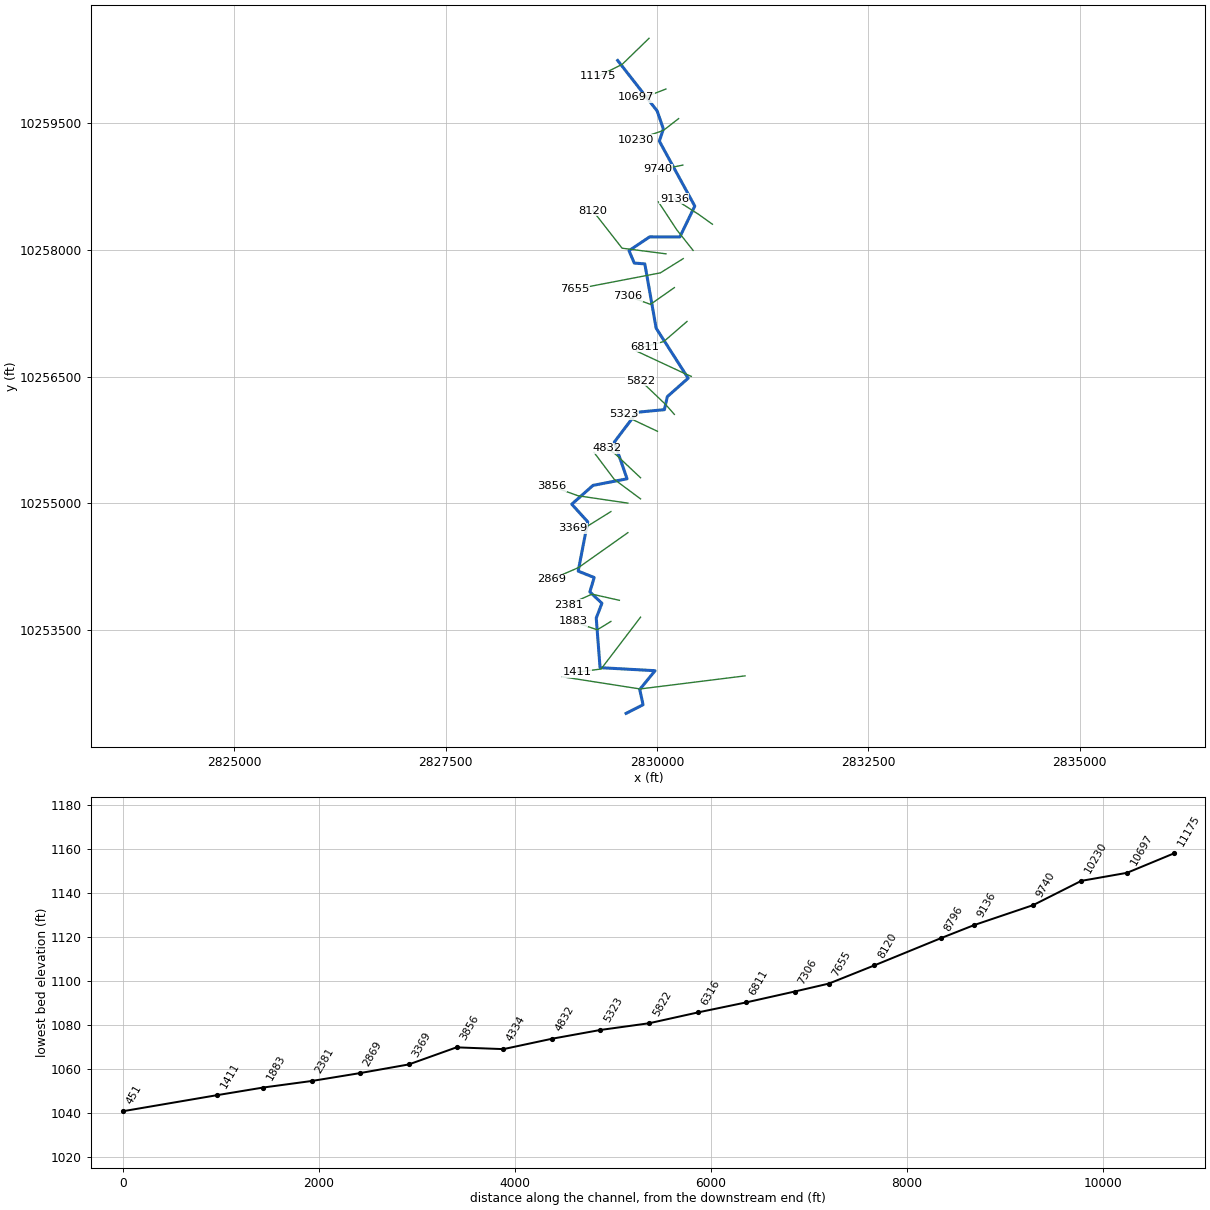
--- LITTLE LLANO 030.prj (project) ---

Proj Title=LITTLE LLANO 030 Base Level Engineering
Current Plan=p01
Default Exp/Contr=0.3,0.1
English Units
Geom File=g01
Flow File=f01
Plan File=p01
BEGIN DESCRIPTION:
LITTLE LLANO 030
END DESCRIPTION:

--- LITTLE LLANO 030.p01 (plan) ---

Plan Title=Multiple Run
Short Identifier=Multiple
Geom File=g01
Flow File=f01
Subcritical Flow
K Sum by GR= 0
Std Step Tol= 0.01
Critical Tol= 0.01
Num of Std Step Trials= 20
Max Error Tol= 0.3
Flow Tol Ratio= 0.001
Split Flow NTrial= 30
Split Flow Tol= 0.02
Split Flow Ratio= 0.02
Log Output Level= 0
Friction Slope Method= 1
Unsteady Friction Slope Method= 2
Unsteady Bridges Friction Slope Method= 1
Parabolic Critical Depth
Global Vel Dist=  1 , 1 , 1
Global Log Level= 0
CheckData=True
Encroach Param= -1, 0, 0, 0
BEGIN DESCRIPTION:
Multiple Run
END DESCRIPTION:

--- LITTLE LLANO 030.f01 (steady flow) ---

Flow Title=Multiple
Number of Profiles=7
Profile Names=10-year,25-year,50-year,1pct_min,100-year,1pct_plu,500-year
River Rch & RM= LITTLE LLANO 030,Reach-1,11175
     499     821    1216     879    1655    3117    2325
Boundary for River Rch & Prof#=LITTLE LLANO 030,Reach-1,1
Up Type=0
Dn Type=3
Dn Slope=0.005
Boundary for River Rch & Prof#=LITTLE LLANO 030,Reach-1,2
Up Type=0
Dn Type=3
Dn Slope=0.005
Boundary for River Rch & Prof#=LITTLE LLANO 030,Reach-1,3
Up Type=0
Dn Type=3
Dn Slope=0.005
Boundary for River Rch & Prof#=LITTLE LLANO 030,Reach-1,4
Up Type=0
Dn Type=3
Dn Slope=0.005
Boundary for River Rch & Prof#=LITTLE LLANO 030,Reach-1,5
Up Type=0
Dn Type=3
Dn Slope=0.005
Boundary for River Rch & Prof#=LITTLE LLANO 030,Reach-1,6
Up Type=0
Dn Type=3
Dn Slope=0.005
Boundary for River Rch & Prof#=LITTLE LLANO 030,Reach-1,7
Up Type=0
Dn Type=3
Dn Slope=0.005

--- LITTLE LLANO 030.g01 (geometry) ---

Geom Title=Existing Conditions

River Reach=LITTLE LLANO 030,Reach-1
Reach XY= 30
      2829535.25     10260241.00      2830002.00     10259644.00
      2830075.50     10259431.00      2830028.25     10259286.00
      2830447.00     10258518.00      2830270.50     10258153.00
      2829913.50     10258154.00      2829669.25     10257990.00
      2829731.50     10257844.00      2829856.50     10257834.00
      2829990.25     10257073.00      2830368.75     10256481.00
      2830122.25     10256263.00      2830088.00     10256109.00
      2829762.50     10256078.00      2829495.50     10255725.00
      2829646.50     10255291.00      2829244.00     10255213.00
      2828992.50     10254990.00      2829181.25     10254782.00
      2829068.50     10254198.00      2829257.25     10254123.00
      2829206.75     10253952.00      2829349.00     10253818.00
      2829282.00     10253643.00      2829327.25     10253056.00
      2829977.50     10253020.00      2829796.50     10252798.00
      2829835.50     10252617.00      2829635.00     10252515.00

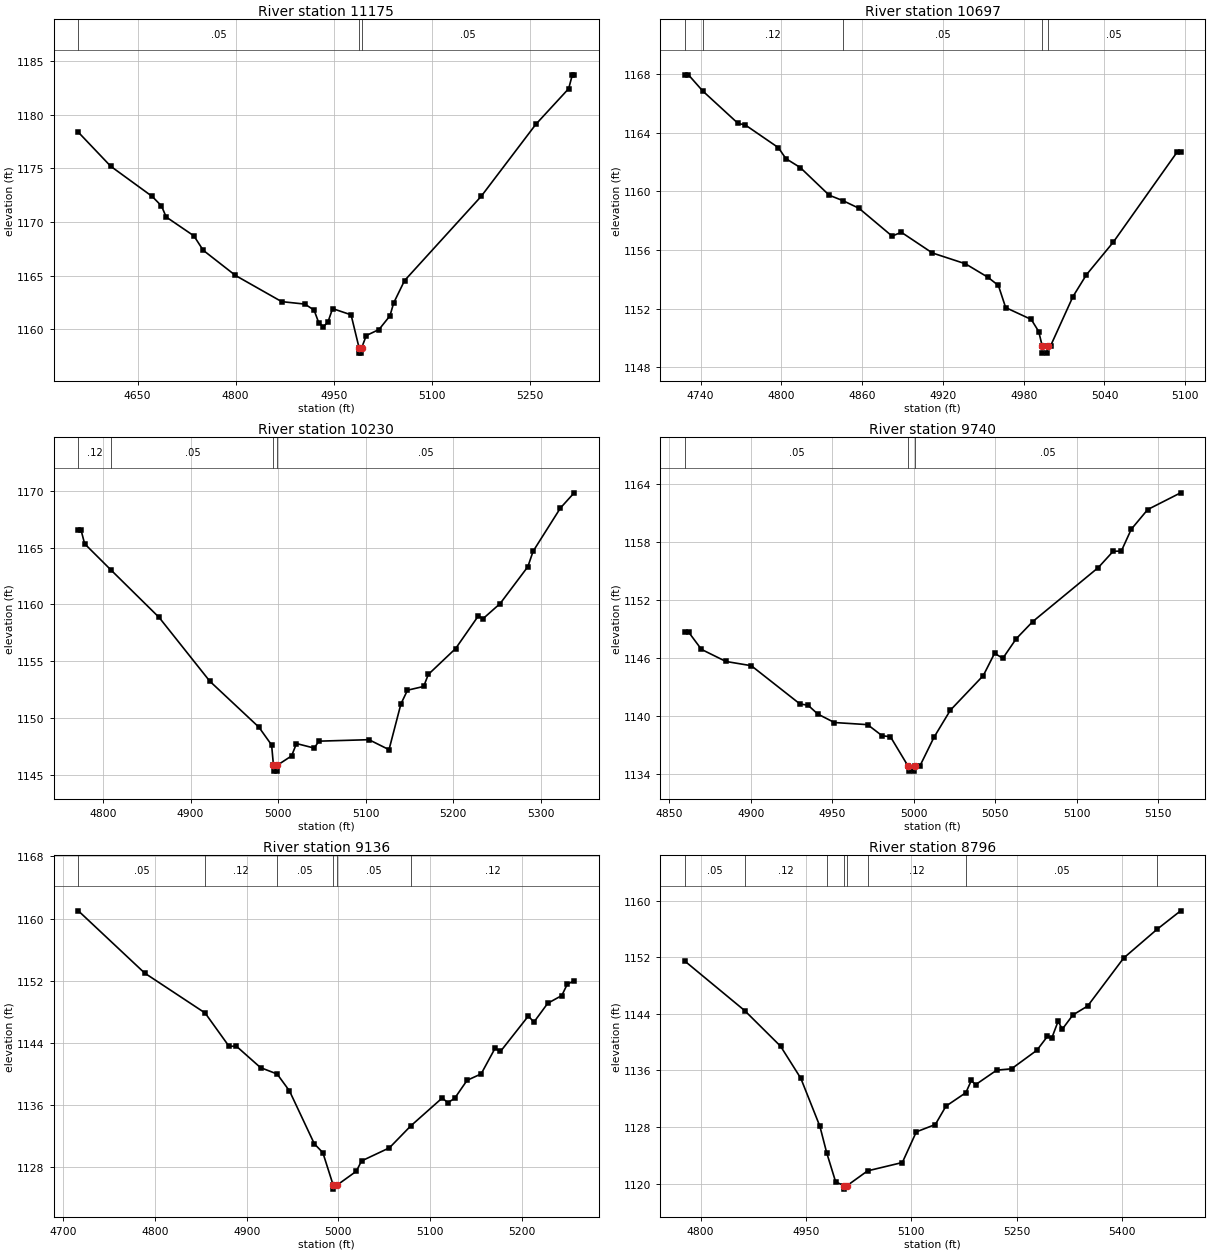
Type RM Length L Ch R = 1,11175,478,478,478
BEGIN DESCRIPTION:
LITTLE LLANO 030 21.0
END DESCRIPTION:
XS GIS Cut Line= 3
      2829905.68     10260503.11      2829589.75     10260196.00
      2829305.67     10260053.10
#Sta/Elev= 30
  4559.4 1178.37  4608.9 1175.20  4672.5 1172.38  4686.6 1171.50  4693.8 1170.47
  4736.2 1168.71  4750.4 1167.37  4799.8 1165.02  4870.5 1162.58  4906.0 1162.35
  4920.1 1161.79  4927.1 1160.63  4934.3 1160.25  4941.2 1160.66  4948.4 1161.93
  4976.7 1161.35  4988.9 1158.28  4989.1 1157.78  4992.6 1157.78  4992.9 1158.28
  5000.0 1159.42  5019.4 1159.98  5036.2 1161.26  5041.8 1162.45  5058.5 1164.54
  5175.7 1172.39  5259.4 1179.11  5309.6 1182.43  5315.2 1183.72  5318.0 1183.72
#Mann=3,-1,0
  4559.4    0.05       0  4988.9    0.03       0  4992.9    0.05       0
Bank Sta=4988.9,4992.9
Exp/Cntr=0.3,0.1

Type RM Length L Ch R = 1,10697,467,467,467
BEGIN DESCRIPTION:
LITTLE LLANO 030 20.0
END DESCRIPTION:
XS GIS Cut Line= 3
      2830105.72     10259903.13      2829852.25     10259805.00
      2829755.67     10259803.11
#Sta/Elev= 30
  4728.2 1167.96  4730.9 1167.96  4741.5 1166.86  4767.8 1164.64  4773.1 1164.54
  4797.7 1162.99  4803.3 1162.24  4814.0 1161.63  4835.5 1159.74  4845.7 1159.37
  4857.6 1158.85  4882.2 1156.95  4889.1 1157.21  4912.1 1155.80  4936.7 1155.06
  4953.4 1154.14  4961.2 1153.58  4966.6 1152.07  4985.6 1151.26  4991.2 1150.43
  4993.7 1149.46  4993.9 1148.96  4997.4 1148.96  4997.7 1149.46  5000.0 1149.46
  5016.6 1152.82  5026.6 1154.31  5046.6 1156.54  5094.1 1162.70  5096.6 1162.70
#Mann=5,-1,0
  4728.2    0.05       0  4741.5    0.12       0  4845.7    0.05       0
  4993.7    0.03       0  4997.7    0.05       0
Bank Sta=4993.7,4997.7
Exp/Cntr=0.3,0.1

Type RM Length L Ch R = 1,10230,490,490,490
BEGIN DESCRIPTION:
LITTLE LLANO 030 19.0
END DESCRIPTION:
XS GIS Cut Line= 3
      2830255.65     10259553.08      2830075.50     10259413.00
      2829755.65     10259303.10
#Sta/Elev= 30
  4771.8 1166.54  4774.9 1166.54  4779.0 1165.33  4809.5 1162.99  4864.1 1158.84
  4922.0 1153.22  4978.1 1149.17  4992.6 1147.60  4994.7 1145.80  4995.0 1145.30
  4998.5 1145.30  4998.7 1145.80  5015.4 1146.64  5021.0 1147.73  5041.3 1147.33
  5046.6 1147.94  5103.8 1148.07  5126.7 1147.19  5140.3 1151.22  5147.8 1152.43
  5166.3 1152.76  5171.6 1153.82  5202.8 1156.10  5228.8 1158.98  5234.1 1158.73
  5253.6 1160.06  5285.3 1163.31  5291.3 1164.67  5322.5 1168.48  5338.2 1169.82
#Mann=4,-1,0
  4771.8    0.12       0  4809.5    0.05       0  4994.7    0.05       0
  4998.7    0.05       0
Bank Sta=4994.7,4998.7
Exp/Cntr=0.3,0.1

Type RM Length L Ch R = 1,9740,604,604,604
BEGIN DESCRIPTION:
LITTLE LLANO 030 18.0
END DESCRIPTION:
XS GIS Cut Line= 3
      2830305.66     10259003.11      2830168.00     10258975.00
      2830005.67     10258953.11
#Sta/Elev= 30
  4859.5 1148.65  4862.0 1148.65  4869.7 1146.90  4884.7 1145.65  4900.3 1145.21
  4930.1 1141.26  4935.2 1141.11  4941.1 1140.21  4951.3 1139.33  4971.7 1139.11
  4980.6 1137.96  4985.7 1137.86  4996.6 1134.80  4996.9 1134.30  5000.4 1134.30
  5000.6 1134.80  5003.7 1134.80  5012.4 1137.79  5022.5 1140.61  5042.7 1144.19
  5049.6 1146.49  5054.7 1145.98  5062.9 1148.00  5073.0 1149.77  5113.3 1155.37
  5122.4 1157.05  5127.4 1157.07  5133.5 1159.33  5143.6 1161.37  5163.8 1163.10
#Mann=3,-1,0
  4859.5    0.05       0  4996.6    0.05       0  5000.6    0.05       0
Bank Sta=4996.6,5000.6
Exp/Cntr=0.3,0.1

Type RM Length L Ch R = 1,9136,340,340,340
BEGIN DESCRIPTION:
LITTLE LLANO 030 17.0
END DESCRIPTION:
XS GIS Cut Line= 3
      2830655.68     10258303.12      2830492.89     10258419.99
      2830205.70     10258603.10
#Sta/Elev= 30
  4716.2 1161.00  4788.6 1152.99  4854.5 1147.86  4880.7 1143.56  4888.5 1143.60
  4915.0 1140.83  4933.1 1140.01  4946.6 1137.83  4973.7 1131.03  4983.0 1129.89
  4994.3 1125.70  4994.6 1125.20  4998.3 1125.70  5019.4 1127.49  5025.3 1128.83
  5055.6 1130.51  5078.8 1133.32  5113.3 1136.93  5119.3 1136.31  5126.8 1136.88
  5140.4 1139.20  5155.7 1140.02  5170.9 1143.32  5176.8 1142.91  5207.3 1147.48
  5213.2 1146.67  5228.4 1149.11  5243.7 1150.10  5249.6 1151.54  5257.2 1152.01
#Mann=6,-1,0
  4716.2    0.05       0  4854.5    0.12       0  4933.1    0.05       0
  4994.3    0.05       0  4998.3    0.05       0  5078.8    0.12       0
Bank Sta=4994.3,4998.3
Exp/Cntr=0.3,0.1

Type RM Length L Ch R = 1,8796,676,676,676
BEGIN DESCRIPTION:
LITTLE LLANO 030 16.0
END DESCRIPTION:
XS GIS Cut Line= 3
      2830427.26     10257993.57      2830236.06     10258234.61
      2830017.25     10258567.59
#Sta/Elev= 30
  4777.4 1151.45  4862.6 1144.46  4913.8 1139.42  4942.6 1134.89  4969.8 1128.10
  4979.4 1124.39  4992.3 1120.23  5004.6 1119.73  5004.8 1119.23  5008.6 1119.73
  5037.7 1121.81  5087.2 1122.99  5107.1 1127.32  5134.2 1128.36  5149.3 1130.95
  5177.7 1132.86  5185.4 1134.58  5191.4 1133.98  5221.6 1136.04  5242.7 1136.23
  5278.8 1138.85  5293.9 1140.82  5299.9 1140.54  5309.0 1142.94  5315.0 1141.83
  5330.1 1143.84  5351.1 1145.10  5402.4 1151.88  5449.7 1155.92  5483.5 1158.55
#Mann=8,-1,0
  4777.4    0.05       0  4862.6    0.12       0  4979.4    0.05       0
  5004.6    0.05       0  5008.6    0.05       0  5037.7    0.12       0
  5177.7    0.05       0  5449.7    0.12       0
Bank Sta=5004.6,5008.6
Exp/Cntr=0.3,0.1

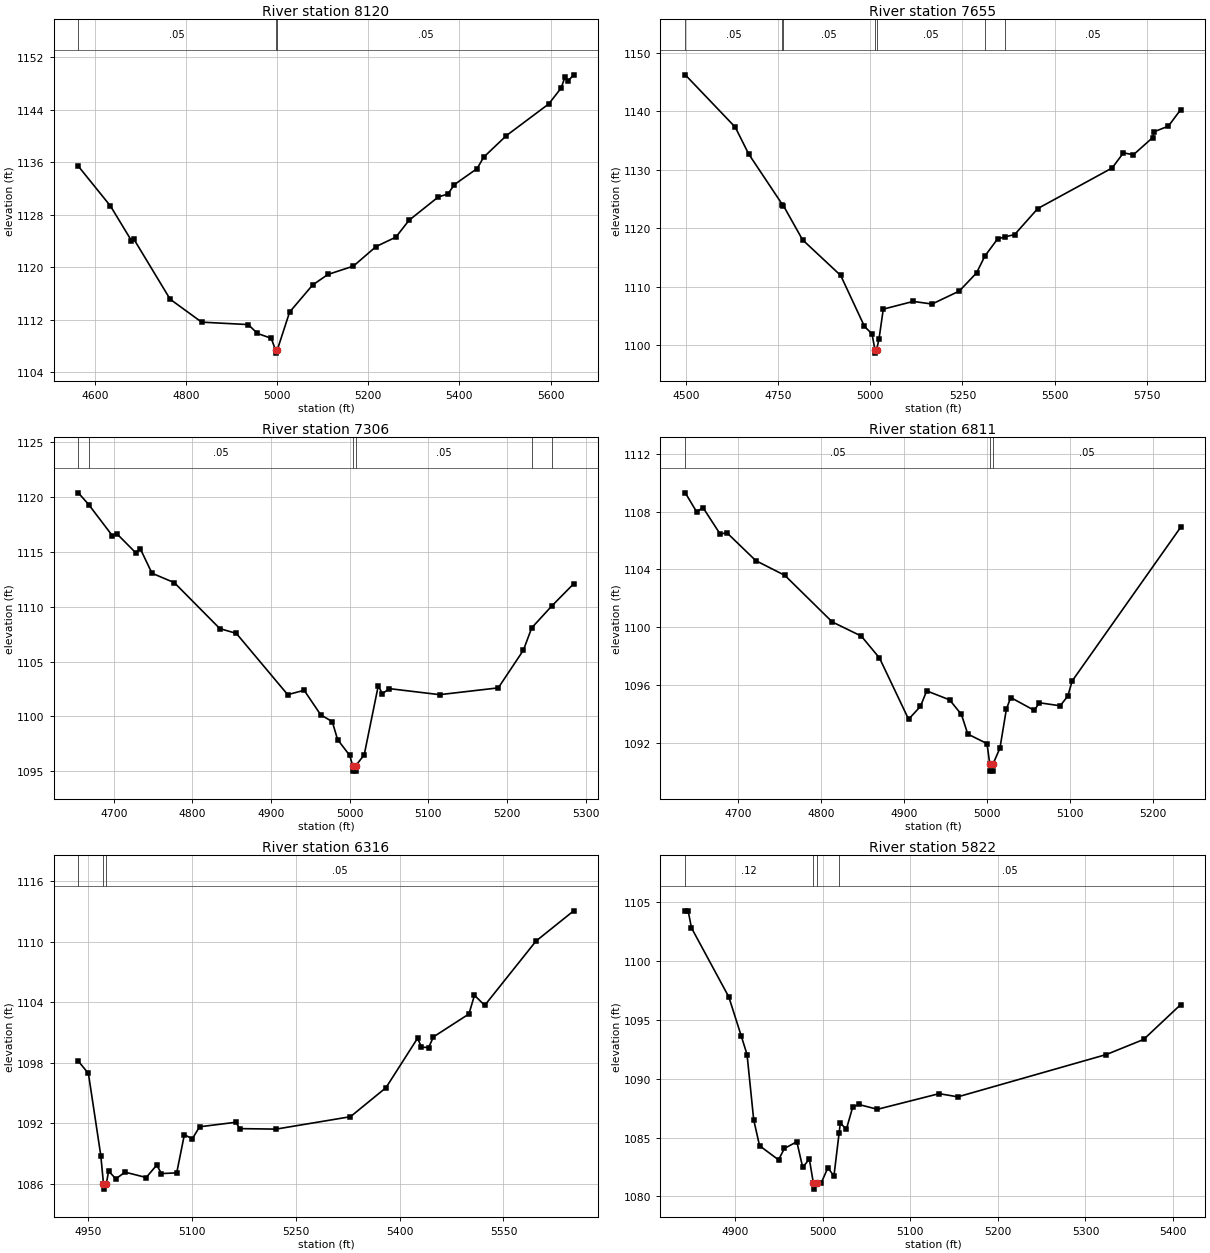
Type RM Length L Ch R = 1,8120,465,465,465
BEGIN DESCRIPTION:
LITTLE LLANO 030 15.0
END DESCRIPTION:
XS GIS Cut Line= 3
      2830105.65     10257953.12      2829587.49     10258019.78
      2829240.24     10258465.31
#Sta/Elev= 30
  4563.5 1135.39  4634.0 1129.33  4680.2 1124.04  4685.3 1124.29  4765.1 1115.12
  4834.2 1111.63  4936.5 1111.26  4956.7 1109.91  4986.9 1109.17  4996.3 1107.41
  4996.5 1106.91  5000.3 1107.41  5027.3 1113.17  5077.8 1117.29  5111.2 1118.89
  5167.3 1120.17  5217.1 1123.15  5260.5 1124.58  5289.4 1127.15  5353.7 1130.71
  5374.5 1131.14  5389.0 1132.59  5438.7 1135.02  5453.2 1136.76  5502.9 1140.04
  5596.1 1144.88  5623.3 1147.30  5631.4 1148.93  5637.7 1148.32  5650.8 1149.31
#Mann=3,-1,0
  4563.5    0.05       0  4996.3    0.05       0  5000.3    0.05       0
Bank Sta=4996.3,5000.3
Exp/Cntr=0.3,0.1

Type RM Length L Ch R = 1,7655,349,349,349
BEGIN DESCRIPTION:
LITTLE LLANO 030 14.0
END DESCRIPTION:
XS GIS Cut Line= 3
      2830310.80     10257896.57      2830040.19     10257727.82
      2829033.14     10257534.28
#Sta/Elev= 30
  4497.7 1146.20  4633.4 1137.25  4669.7 1132.68  4761.5 1124.00  4764.2 1123.82
  4816.1 1117.99  4919.5 1111.91  4984.1 1103.19  5004.5 1101.92  5012.7 1099.13
  5012.9 1098.63  5016.7 1099.13  5023.4 1101.00  5035.1 1106.15  5116.5 1107.47
  5167.4 1107.02  5241.4 1109.24  5288.2 1112.34  5310.6 1115.20  5345.3 1118.15
  5366.6 1118.52  5391.5 1118.89  5454.3 1123.34  5656.2 1130.28  5686.8 1132.86
  5714.0 1132.54  5766.0 1135.46  5771.1 1136.49  5809.0 1137.44  5842.1 1140.24
#Mann=7,-1,0
  4497.7    0.05       0  4761.5    0.12       0  4764.2    0.05       0
  5012.7    0.05       0  5016.7    0.05       0  5310.6    0.12       0
  5366.6    0.05       0
Bank Sta=5012.7,5016.7
Exp/Cntr=0.3,0.1

Type RM Length L Ch R = 1,7306,495,495,495
BEGIN DESCRIPTION:
LITTLE LLANO 030 13.0
END DESCRIPTION:
XS GIS Cut Line= 3
      2830205.69     10257553.12      2829923.00     10257355.00
      2829655.64     10257453.13
#Sta/Elev= 30
  4654.8 1120.39  4668.0 1119.32  4698.0 1116.49  4704.1 1116.64  4727.6 1114.94
  4733.7 1115.28  4748.5 1113.06  4776.9 1112.20  4834.8 1108.01  4855.7 1107.58
  4921.1 1101.99  4942.0 1102.39  4963.0 1100.16  4977.8 1099.53  4984.5 1097.90
  5000.0 1096.45  5003.7 1095.52  5004.0 1095.02  5007.5 1095.02  5007.7 1095.52
  5018.4 1096.51  5036.2 1102.78  5041.6 1102.09  5050.4 1102.54  5114.3 1101.99
  5188.9 1102.61  5220.8 1106.04  5231.4 1108.08  5257.0 1110.08  5284.8 1112.10
#Mann=6,-1,0
  4654.8    0.12       0  4668.0    0.05       0  5003.7    0.05       0
  5007.7    0.05       0  5231.4    0.12       0  5257.0    0.05       0
Bank Sta=5003.7,5007.7
Exp/Cntr=0.3,0.1

Type RM Length L Ch R = 1,6811,495,495,495
BEGIN DESCRIPTION:
LITTLE LLANO 030 12.0
END DESCRIPTION:
XS GIS Cut Line= 3
      2830355.68     10257153.10      2830080.75     10256915.00
      2829855.70     10256853.12
#Sta/Elev= 30
  4636.3 1109.29  4650.0 1107.98  4657.7 1108.27  4678.5 1106.43  4686.2 1106.55
  4721.3 1104.61  4756.4 1103.59  4813.4 1100.38  4848.5 1099.40  4870.4 1097.89
  4905.5 1093.66  4919.8 1094.55  4927.3 1095.62  4954.9 1095.00  4969.2 1093.99
  4976.8 1092.64  5000.0 1091.98  5003.3 1090.58  5003.5 1090.08  5007.0 1090.08
  5007.3 1090.58  5015.6 1091.67  5023.4 1094.37  5028.6 1095.16  5057.1 1094.27
  5063.0 1094.80  5088.2 1094.59  5097.4 1095.26  5102.6 1096.30  5233.4 1106.91
#Mann=3,-1,0
  4636.3    0.05       0  5003.3    0.03       0  5007.3    0.05       0
Bank Sta=5003.3,5007.3
Exp/Cntr=0.3,0.1

Type RM Length L Ch R = 1,6316,494,494,494
BEGIN DESCRIPTION:
LITTLE LLANO 030 11.0
END DESCRIPTION:
XS GIS Cut Line= 3
      2830405.65     10256503.13      2830346.25     10256528.00
      2829755.69     10256803.11
#Sta/Elev= 30
  4935.6 1098.17  4950.2 1096.95  4968.1 1088.82  4972.0 1086.00  4972.2 1085.50
  4976.0 1086.00  4979.4 1087.29  4989.8 1086.52  5003.2 1087.18  5033.7 1086.65
  5048.9 1087.88  5055.8 1087.04  5077.8 1087.11  5088.9 1090.90  5100.2 1090.47
  5110.9 1091.67  5163.3 1092.12  5168.8 1091.49  5221.3 1091.44  5328.9 1092.67
  5380.2 1095.54  5425.9 1100.44  5431.5 1099.55  5441.9 1099.52  5448.8 1100.57
  5500.1 1102.84  5508.1 1104.69  5522.9 1103.69  5597.1 1110.06  5651.5 1113.05
#Mann=3,-1,0
  4935.6    0.05       0  4972.0    0.05       0  4976.0    0.05       0
Bank Sta=4972,4976
Exp/Cntr=0.3,0.1

Type RM Length L Ch R = 1,5822,499,499,499
BEGIN DESCRIPTION:
LITTLE LLANO 030 10.0
END DESCRIPTION:
XS GIS Cut Line= 3
      2830205.67     10256053.13      2830101.50     10256171.00
      2829805.66     10256453.13
#Sta/Elev= 30
  4842.7 1104.29  4846.0 1104.29  4849.8 1102.84  4892.5 1096.96  4906.7 1093.64
  4913.3 1092.07  4920.9 1086.52  4927.6 1084.31  4949.3 1083.11  4956.0 1084.08
  4970.2 1084.65  4976.9 1082.47  4984.5 1083.18  4989.1 1081.12  4989.4 1080.62
  4993.1 1081.12  4998.1 1081.15  5005.7 1082.44  5012.6 1081.73  5018.5 1085.38
  5019.9 1086.24  5026.8 1085.71  5034.0 1087.59  5040.9 1087.82  5062.3 1087.41
  5132.8 1088.74  5154.2 1088.47  5324.0 1092.07  5366.5 1093.35  5408.8 1096.31
#Mann=4,-1,0
  4842.7    0.12       0  4989.1    0.07       0  4993.1    0.12       0
  5018.5    0.05       0
Bank Sta=4989.1,4993.1
Exp/Cntr=0.3,0.1

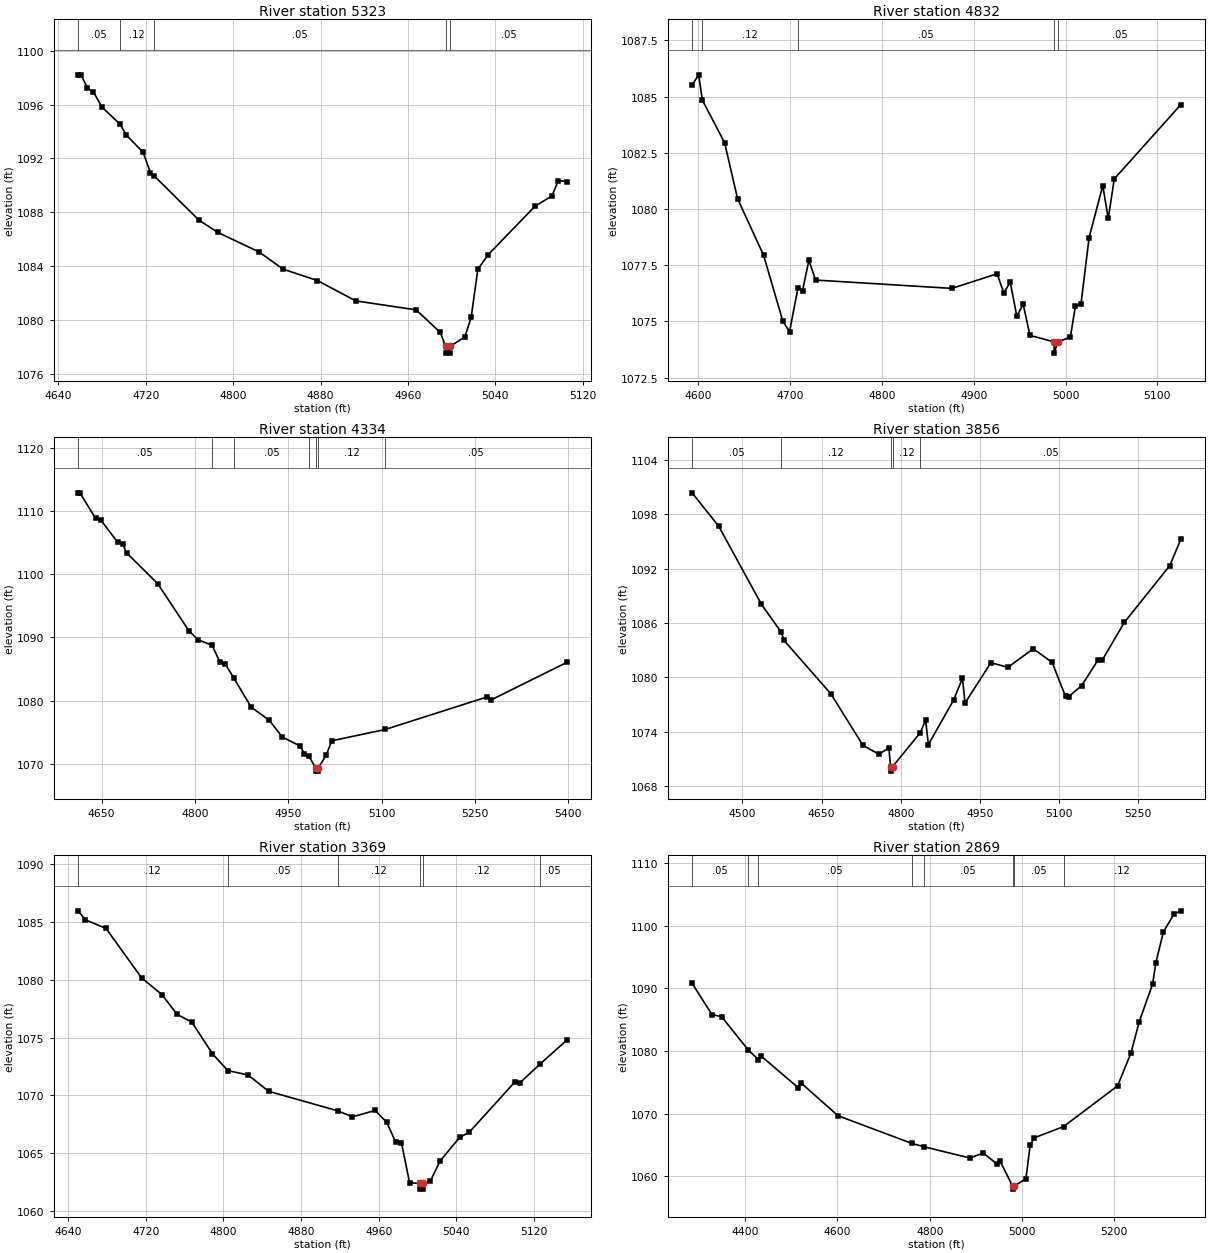
Type RM Length L Ch R = 1,5323,491,491,491
BEGIN DESCRIPTION:
LITTLE LLANO 030 9.0
END DESCRIPTION:
XS GIS Cut Line= 3
      2830005.68     10255853.11      2829696.25     10255999.00
      2829605.68     10256053.11
#Sta/Elev= 30
  4657.9 1098.21  4660.7 1098.21  4666.5 1097.24  4672.1 1096.93  4680.0 1095.80
  4696.4 1094.55  4702.1 1093.74  4717.6 1092.45  4724.2 1090.95  4727.6 1090.71
  4768.7 1087.42  4786.0 1086.51  4823.7 1085.06  4845.8 1083.78  4877.1 1082.94
  4912.2 1081.43  4967.5 1080.76  4989.6 1079.09  4994.5 1078.05  4994.8 1077.55
  4998.3 1077.55  4998.5 1078.05  5012.1 1078.75  5017.9 1080.20  5024.0 1083.77
  5033.5 1084.86  5076.3 1088.45  5091.9 1089.22  5097.7 1090.36  5105.5 1090.29
#Mann=5,-1,0
  4657.9    0.05       0  4696.4    0.12       0  4727.6    0.05       0
  4994.5    0.03       0  4998.5    0.05       0
Bank Sta=4994.5,4998.5
Exp/Cntr=0.3,0.1

Type RM Length L Ch R = 1,4832,498,498,498
BEGIN DESCRIPTION:
LITTLE LLANO 030 8.0
END DESCRIPTION:
XS GIS Cut Line= 3
      2829805.67     10255303.13      2829509.50     10255582.00
      2829405.71     10255653.09
#Sta/Elev= 30
  4593.2 1085.51  4600.3 1085.97  4604.4 1084.84  4628.6 1082.95  4642.7 1080.46
  4671.1 1077.94  4692.1 1075.00  4699.4 1074.55  4708.5 1076.49  4713.5 1076.37
  4720.4 1077.72  4727.7 1076.84  4876.2 1076.47  4925.5 1077.12  4932.8 1076.26
  4939.7 1076.75  4947.0 1075.23  4953.9 1075.77  4961.2 1074.38  4987.5 1074.09
  4987.7 1073.59  4991.5 1074.09  5005.3 1074.30  5010.8 1075.69  5016.8 1075.76
  5025.7 1078.73  5040.6 1081.04  5046.6 1079.58  5053.1 1081.34  5125.8 1084.65
#Mann=5,-1,0
  4593.2    0.05       0  4604.4    0.12       0  4708.5    0.05       0
  4987.5    0.03       0  4991.5    0.05       0
Bank Sta=4987.5,4991.5
Exp/Cntr=0.3,0.1

Type RM Length L Ch R = 1,4334,478,478,478
BEGIN DESCRIPTION:
LITTLE LLANO 030 7.0
END DESCRIPTION:
XS GIS Cut Line= 3
      2829805.70     10255053.10      2829494.50     10255285.00
      2829255.67     10255603.13
#Sta/Elev= 30
  4611.9 1112.85  4615.0 1112.85  4640.1 1108.83  4648.4 1108.57  4675.5 1105.06
  4683.9 1104.72  4690.1 1103.36  4740.1 1098.48  4790.2 1091.04  4804.8 1089.62
  4827.4 1088.77  4840.2 1086.05  4848.6 1085.80  4862.7 1083.53  4890.3 1078.96
  4919.5 1076.89  4940.3 1074.25  4969.5 1072.79  4975.8 1071.56  4982.8 1071.25
  4994.1 1069.35  4994.4 1068.85  4997.9 1068.85  4998.1 1069.35  5011.4 1071.44
  5019.7 1073.64  5105.9 1075.44  5269.7 1080.58  5275.9 1080.10  5397.8 1086.04
#Mann=7,-1,0
  4611.9    0.05       0  4827.4    0.12       0  4862.7    0.05       0
  4982.8    0.12       0  4994.1    0.07       0  4998.1    0.12       0
  5105.9    0.05       0
Bank Sta=4994.1,4998.1
Exp/Cntr=0.3,0.1

Type RM Length L Ch R = 1,3856,487,487,487
BEGIN DESCRIPTION:
LITTLE LLANO 030 6.0
END DESCRIPTION:
XS GIS Cut Line= 3
      2829655.68     10255003.11      2829066.75     10255090.00
      2828755.68     10255203.11
#Sta/Elev= 30
  4404.7 1100.37  4455.2 1096.67  4536.1 1088.06  4573.6 1084.99  4578.8 1084.08
  4667.5 1078.20  4728.2 1072.52  4758.5 1071.52  4777.6 1072.23  4780.6 1070.16
  4780.9 1069.66  4784.6 1070.16  4837.1 1073.91  4847.2 1075.29  4852.3 1072.59
  4900.0 1077.48  4916.9 1079.91  4921.9 1077.19  4970.8 1081.62  5003.2 1081.12
  5051.0 1083.16  5086.9 1081.66  5112.2 1077.90  5118.2 1077.88  5142.8 1079.10
  5173.4 1081.88  5182.0 1081.93  5223.9 1086.09  5309.7 1092.33  5331.0 1095.28
#Mann=5,-1,0
  4404.7    0.05       0  4573.6    0.12       0  4780.6    0.05       0
  4784.6    0.12       0  4837.1    0.05       0
Bank Sta=4780.6,4784.6
Exp/Cntr=0.3,0.1

Type RM Length L Ch R = 1,3369,500,500,500
BEGIN DESCRIPTION:
LITTLE LLANO 030 5.0
END DESCRIPTION:
XS GIS Cut Line= 3
      2829455.68     10254903.11      2829158.75     10254718.00
      2829005.67     10254703.11
#Sta/Elev= 30
  4650.1 1085.96  4657.8 1085.18  4679.0 1084.44  4715.6 1080.17  4736.8 1078.70
  4752.2 1077.01  4767.5 1076.33  4788.7 1073.60  4804.4 1072.15  4825.3 1071.77
  4846.5 1070.36  4917.7 1068.67  4932.9 1068.15  4956.3 1068.70  4968.3 1067.67
  4977.5 1065.95  4983.4 1065.90  4991.8 1062.45  5002.1 1062.40  5002.3 1061.90
  5005.8 1061.90  5006.1 1062.40  5013.1 1062.58  5023.2 1064.33  5043.3 1066.37
  5053.3 1066.82  5100.3 1071.17  5105.4 1071.09  5125.9 1072.69  5153.8 1074.78
#Mann=6,-1,0
  4650.1    0.12       0  4804.4    0.05       0  4917.7    0.12       0
  5002.1    0.07       0  5006.1    0.12       0  5125.9    0.05       0
Bank Sta=5002.1,5006.1
Exp/Cntr=0.3,0.1

Type RM Length L Ch R = 1,2869,488,488,488
BEGIN DESCRIPTION:
LITTLE LLANO 030 4.0
END DESCRIPTION:
XS GIS Cut Line= 3
      2829655.70     10254653.12      2829072.00     10254240.00
      2828755.65     10254103.10
#Sta/Elev= 30
  4284.9 1090.80  4328.0 1085.81  4348.9 1085.47  4407.1 1080.11  4428.7 1078.63
  4435.1 1079.16  4515.1 1074.12  4521.2 1074.88  4601.2 1069.66  4761.6 1065.23
  4787.1 1064.72  4886.7 1062.91  4916.3 1063.70  4945.8 1061.95  4952.0 1062.50
  4979.5 1058.44  4979.8 1057.94  4983.5 1058.44  5008.5 1059.58  5017.8 1065.01
  5026.6 1066.13  5090.2 1067.93  5207.3 1074.43  5236.3 1079.68  5254.3 1084.69
  5283.2 1090.68  5290.2 1094.09  5306.7 1099.03  5330.2 1101.93  5344.7 1102.38
#Mann=8,-1,0
  4284.9    0.05       0  4407.1    0.12       0  4428.7    0.05       0
  4761.6    0.12       0  4787.1    0.05       0  4979.5    0.05       0
  4983.5    0.05       0  5090.2    0.12       0
Bank Sta=4979.5,4983.5
Exp/Cntr=0.3,0.1

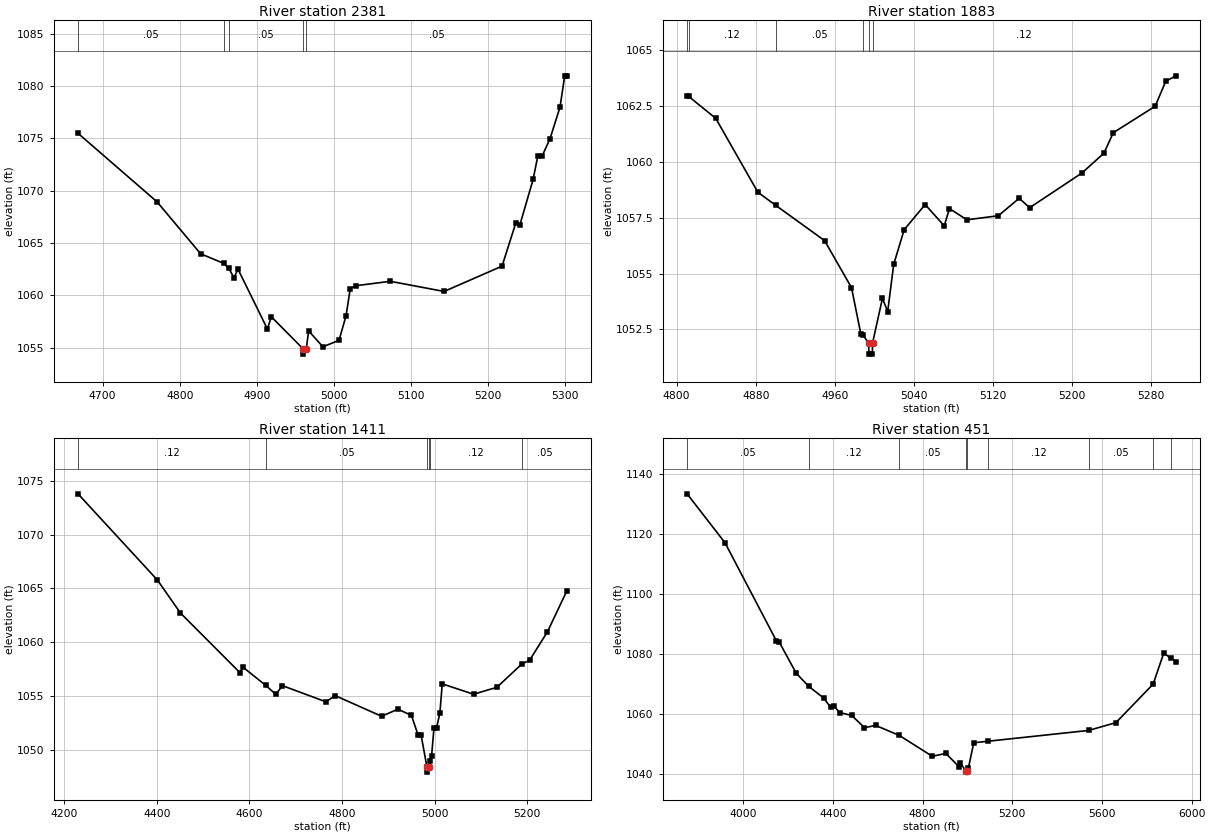
Type RM Length L Ch R = 1,2381,498,498,498
BEGIN DESCRIPTION:
LITTLE LLANO 030 3.0
END DESCRIPTION:
XS GIS Cut Line= 3
      2829555.65     10253853.12      2829231.75     10253926.00
      2828955.67     10253803.10
#Sta/Elev= 30
  4668.0 1075.50  4770.5 1068.95  4827.1 1063.98  4857.2 1063.06  4863.7 1062.58
  4870.4 1061.69  4875.5 1062.52  4913.7 1056.79  4918.8 1057.96  4960.1 1054.89
  4960.3 1054.39  4964.1 1054.89  4967.2 1056.61  4985.7 1055.09  5006.6 1055.71
  5015.8 1058.07  5021.2 1060.66  5028.5 1060.93  5073.2 1061.35  5142.9 1060.38
  5218.1 1062.80  5235.9 1066.92  5241.3 1066.76  5258.4 1071.09  5264.6 1073.37
  5270.1 1073.32  5280.3 1074.98  5293.3 1078.00  5299.4 1080.99  5302.2 1080.99
#Mann=5,-1,0
  4668.0    0.05       0  4857.2    0.12       0  4863.7    0.05       0
  4960.1    0.05       0  4964.1    0.05       0
Bank Sta=4960.1,4964.1
Exp/Cntr=0.3,0.1

Type RM Length L Ch R = 1,1883,472,472,472
BEGIN DESCRIPTION:
LITTLE LLANO 030 2.0
END DESCRIPTION:
XS GIS Cut Line= 3
      2829455.66     10253603.10      2829294.25     10253504.00
      2829005.70     10253603.11
#Sta/Elev= 30
  4810.6 1062.91  4812.2 1062.91  4839.6 1061.93  4882.2 1058.63  4900.1 1058.05
  4949.7 1056.47  4976.9 1054.37  4986.4 1052.29  4988.7 1052.24  4994.2 1051.90
  4994.5 1051.40  4998.0 1051.40  4998.2 1051.90  5008.2 1053.89  5013.5 1053.30
  5019.6 1055.41  5030.2 1056.96  5051.4 1058.08  5070.7 1057.13  5076.0 1057.90
  5093.6 1057.40  5125.4 1057.58  5146.5 1058.36  5157.1 1057.94  5210.0 1059.49
  5232.3 1060.38  5241.7 1061.29  5284.0 1062.47  5294.8 1063.59  5305.1 1063.83
#Mann=6,-1,0
  4810.6    0.05       0  4812.2    0.12       0  4900.1    0.05       0
  4988.7    0.12       0  4994.2    0.07       0  4998.2    0.12       0
Bank Sta=4994.2,4998.2
Exp/Cntr=0.3,0.1

Type RM Length L Ch R = 1,1411,960,960,960
BEGIN DESCRIPTION:
LITTLE LLANO 030 1.0
END DESCRIPTION:
XS GIS Cut Line= 3
      2829805.70     10253653.14      2829339.25     10253040.00
      2829055.64     10253003.11
#Sta/Elev= 30
  4229.6 1073.78  4401.2 1065.77  4451.1 1062.70  4579.9 1057.15  4586.2 1057.67
  4635.3 1055.98  4657.0 1055.15  4671.5 1055.95  4765.0 1054.46  4785.8 1055.02
  4885.7 1053.11  4921.0 1053.77  4950.1 1053.19  4964.6 1051.36  4971.0 1051.36
  4983.5 1048.42  4983.7 1047.92  4987.5 1048.42  4990.9 1048.98  4993.7 1049.45
  4998.8 1052.01  5004.3 1052.01  5011.6 1053.41  5016.7 1056.12  5084.3 1055.16
  5134.7 1055.80  5188.8 1057.97  5205.3 1058.31  5243.9 1060.95  5286.0 1064.77
#Mann=6,-1,0
  4229.6    0.12       0  4635.3    0.05       0  4983.5    0.07       0
  4987.5    0.05       0  4990.9    0.12       0  5188.8    0.05       0
Bank Sta=4983.5,4987.5
Exp/Cntr=0.3,0.1

Type RM Length L Ch R = 1,451,0,0,0
BEGIN DESCRIPTION:
WRIGHTS CREEK 34.0
END DESCRIPTION:
XS GIS Cut Line= 3
      2831040.63     10252958.75      2829800.25     10252804.00
      2828881.35     10252947.89
#Sta/Elev= 30
  3750.0 1133.36  3919.0 1117.07  4148.0 1084.42  4161.1 1083.92  4236.7 1073.59
  4292.8 1069.18  4359.6 1065.30  4389.9 1062.20  4403.2 1062.82  4430.2 1060.48
  4483.9 1059.52  4541.0 1055.46  4591.4 1056.18  4696.3 1052.86  4843.4 1045.91
  4903.8 1046.85  4963.0 1042.41  4968.1 1043.66  4992.5 1041.13  4992.8 1040.63
  4996.5 1041.13  5004.8 1042.12  5028.3 1050.41  5093.8 1050.94  5540.4 1054.52
  5662.5 1057.13  5828.4 1069.97  5875.1 1080.20  5907.3 1078.67  5930.1 1077.48
#Mann=9,-1,0
  3750.0    0.05       0  4292.8    0.12       0  4696.3    0.05       0
  4992.5    0.03       0  4996.5    0.05       0  5093.8    0.12       0
  5540.4    0.05       0  5828.4    0.12       0  5907.3    0.05       0
Bank Sta=4992.5,4996.5
Exp/Cntr=0.3,0.1

Chan Stop Cuts=-1