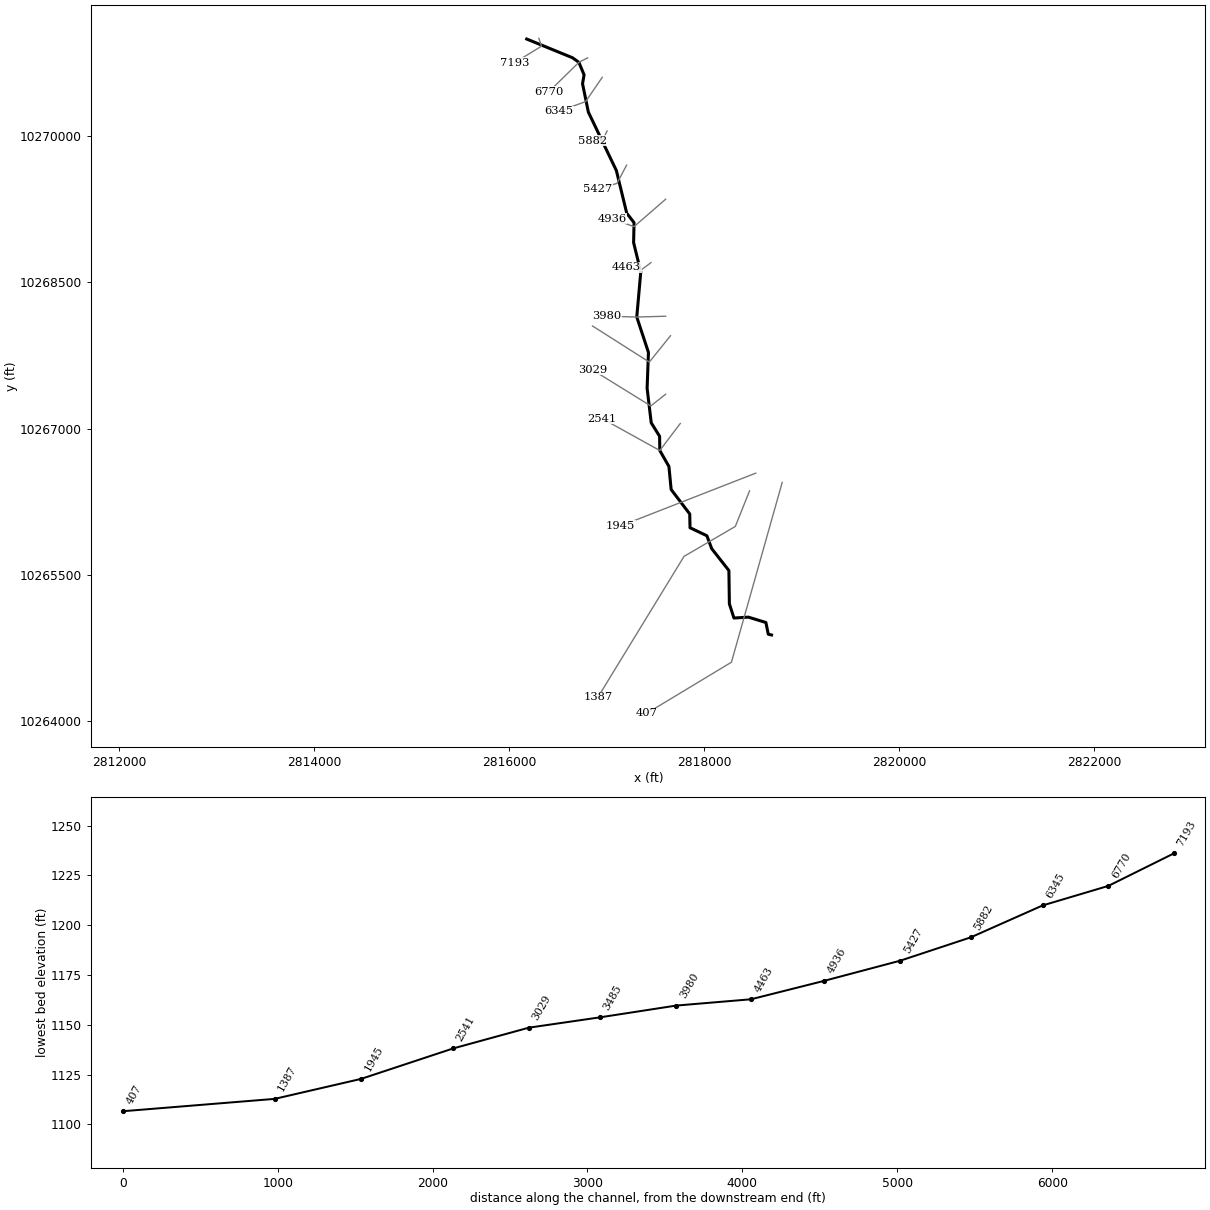
--- LITTLE LLANO 032.prj (project) ---

Proj Title=LITTLE LLANO 032 Base Level Engineering
Current Plan=p01
Default Exp/Contr=0.3,0.1
English Units
Geom File=g01
Flow File=f01
Plan File=p01
BEGIN DESCRIPTION:
LITTLE LLANO 032
END DESCRIPTION:

--- LITTLE LLANO 032.p01 (plan) ---

Plan Title=Multiple Run
Short Identifier=Multiple
Geom File=g01
Flow File=f01
Subcritical Flow
K Sum by GR= 0
Std Step Tol= 0.01
Critical Tol= 0.01
Num of Std Step Trials= 20
Max Error Tol= 0.3
Flow Tol Ratio= 0.001
Split Flow NTrial= 30
Split Flow Tol= 0.02
Split Flow Ratio= 0.02
Log Output Level= 0
Friction Slope Method= 1
Unsteady Friction Slope Method= 2
Unsteady Bridges Friction Slope Method= 1
Parabolic Critical Depth
Global Vel Dist=  1 , 1 , 1
Global Log Level= 0
CheckData=True
Encroach Param= -1, 0, 0, 0
BEGIN DESCRIPTION:
Multiple Run
END DESCRIPTION:

--- LITTLE LLANO 032.f01 (steady flow) ---

Flow Title=Multiple
Number of Profiles=7
Profile Names=10-year,25-year,50-year,1pct_min,100-year,1pct_plu,500-year
River Rch & RM= LITTLE LLANO 032,Reach-1,7193
     267     421     867     697    1209    2097    1791
Boundary for River Rch & Prof#=LITTLE LLANO 032,Reach-1,1
Up Type=0
Dn Type=3
Dn Slope=0.005
Boundary for River Rch & Prof#=LITTLE LLANO 032,Reach-1,2
Up Type=0
Dn Type=3
Dn Slope=0.005
Boundary for River Rch & Prof#=LITTLE LLANO 032,Reach-1,3
Up Type=0
Dn Type=3
Dn Slope=0.005
Boundary for River Rch & Prof#=LITTLE LLANO 032,Reach-1,4
Up Type=0
Dn Type=3
Dn Slope=0.005
Boundary for River Rch & Prof#=LITTLE LLANO 032,Reach-1,5
Up Type=0
Dn Type=3
Dn Slope=0.005
Boundary for River Rch & Prof#=LITTLE LLANO 032,Reach-1,6
Up Type=0
Dn Type=3
Dn Slope=0.005
Boundary for River Rch & Prof#=LITTLE LLANO 032,Reach-1,7
Up Type=0
Dn Type=3
Dn Slope=0.005

--- LITTLE LLANO 032.g01 (geometry) ---

Geom Title=Existing Conditions

River Reach=LITTLE LLANO 032,Reach-1
Reach XY= 30
      2816181.00     10270996.00      2816650.50     10270804.00
      2816716.00     10270757.00      2816769.25     10270629.00
      2816753.50     10270538.00      2816813.00     10270247.00
      2817100.50     10269647.00      2817206.75     10269210.00
      2817281.75     10269113.00      2817277.25     10268908.00
      2817350.75     10268608.00      2817309.75     10268145.00
      2817429.50     10267782.00      2817415.75     10267414.00
      2817458.00     10267060.00      2817543.75     10266922.00
      2817546.00     10266776.00      2817639.50     10266612.00
      2817662.25     10266376.00      2817853.00     10266125.00
      2817855.75     10265984.00      2818028.50     10265902.00
      2818078.50     10265769.00      2818254.50     10265545.00
      2818259.50     10265203.00      2818306.25     10265058.00
      2818454.50     10265067.00      2818634.00     10265012.00
      2818658.25     10264892.00      2818691.75     10264884.00

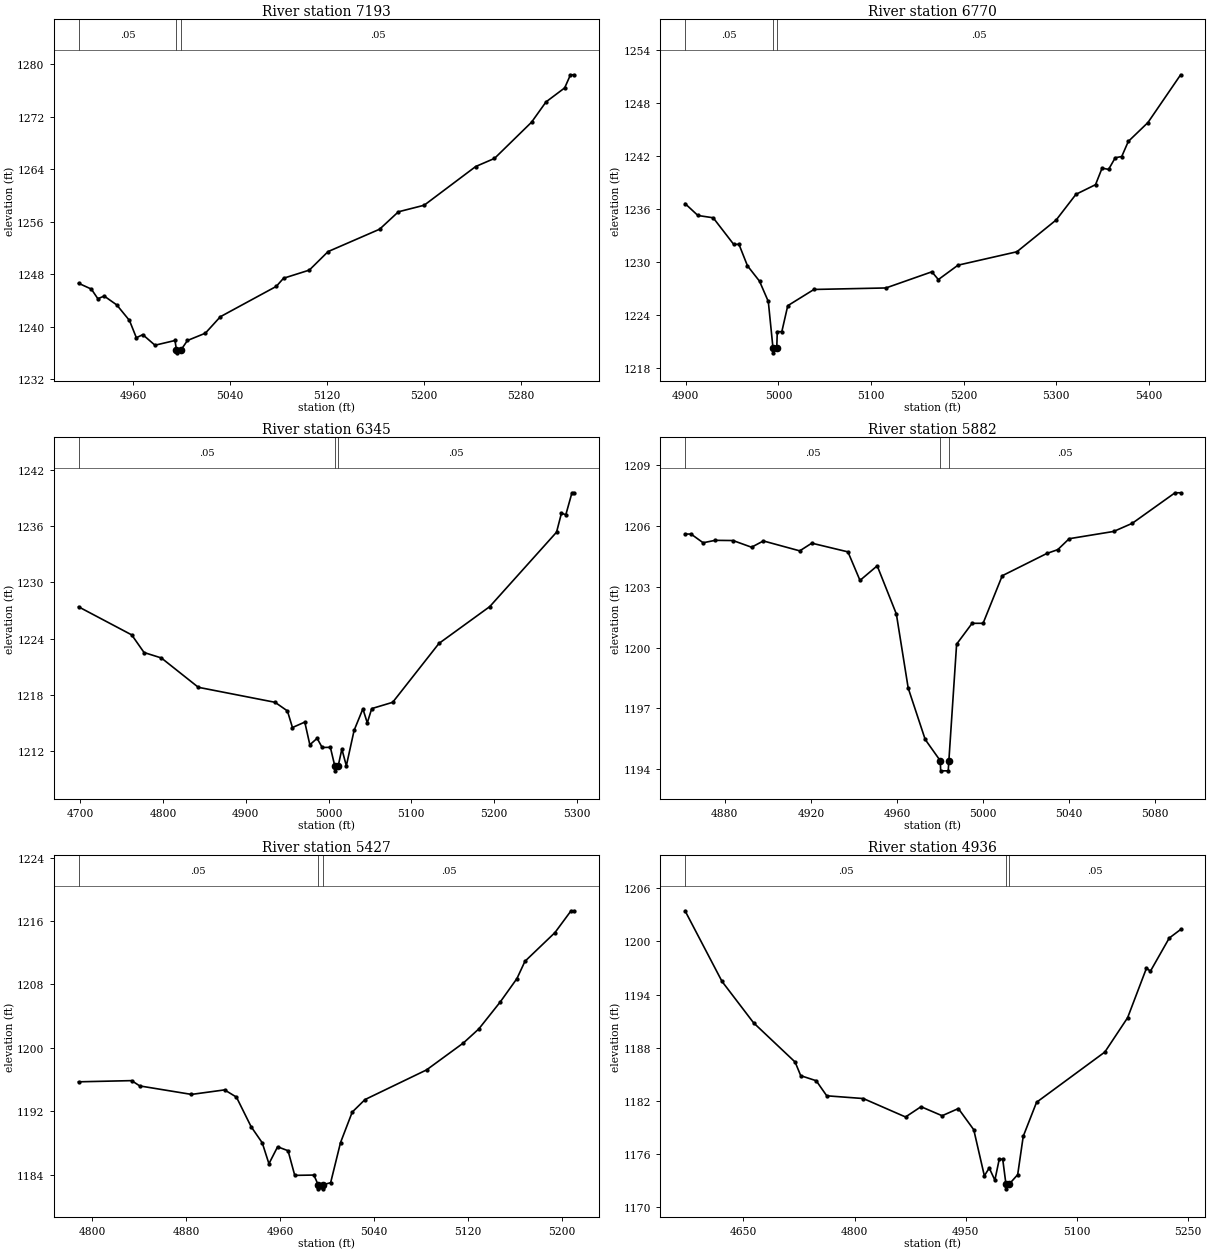
Type RM Length L Ch R = 1,7193,423,423,423
BEGIN DESCRIPTION:
LITTLE LLANO 032 12.0
END DESCRIPTION:
XS GIS Cut Line= 3
      2816305.67     10271003.16      2816332.25     10270922.00
      2816055.65     10270753.09
#Sta/Elev= 30
  4914.6 1246.64  4925.2 1245.75  4930.6 1244.28  4935.8 1244.69  4946.2 1243.34
  4956.7 1240.97  4962.4 1238.34  4967.7 1238.81  4977.8 1237.20  4994.3 1237.92
  4995.5 1236.54  4995.7 1236.04  4999.5 1236.54  5004.6 1237.92  5019.4 1239.03
  5031.8 1241.54  5078.0 1246.16  5084.0 1247.40  5105.3 1248.64  5120.8 1251.46
  5163.4 1254.87  5178.9 1257.52  5200.2 1258.52  5242.8 1264.42  5258.3 1265.65
  5288.9 1271.16  5300.9 1274.26  5316.3 1276.39  5321.1 1278.39  5324.1 1278.39
#Mann=3,-1,0
  4914.6    0.05       0  4995.5    0.05       0  4999.5    0.05       0
Bank Sta=4995.5,4999.5
Exp/Cntr=0.3,0.1

Type RM Length L Ch R = 1,6770,425,425,425
BEGIN DESCRIPTION:
LITTLE LLANO 032 11.0
END DESCRIPTION:
XS GIS Cut Line= 3
      2816805.64     10270803.09      2816716.00     10270757.00
      2816405.71     10270453.13
#Sta/Elev= 30
  4899.2 1236.64  4913.1 1235.29  4929.6 1235.03  4951.8 1232.01  4957.4 1232.03
  4966.6 1229.59  4979.6 1227.85  4989.1 1225.55  4994.2 1220.23  4994.4 1219.73
  4998.2 1220.23  4998.8 1222.13  5003.7 1222.13  5010.1 1225.07  5038.4 1226.91
  5116.1 1227.08  5165.7 1228.91  5172.7 1228.03  5193.9 1229.66  5257.5 1231.18
  5300.0 1234.79  5321.3 1237.69  5342.4 1238.78  5349.5 1240.66  5356.5 1240.51
  5363.7 1241.83  5370.7 1241.97  5377.8 1243.68  5399.0 1245.82  5434.3 1251.23
#Mann=3,-1,0
  4899.2    0.05       0  4994.2    0.05       0  4998.2    0.05       0
Bank Sta=4994.2,4998.2
Exp/Cntr=0.3,0.1

Type RM Length L Ch R = 1,6345,463,463,463
BEGIN DESCRIPTION:
LITTLE LLANO 032 10.0
END DESCRIPTION:
XS GIS Cut Line= 3
      2816955.67     10270603.10      2816784.75     10270354.00
      2816505.72     10270253.13
#Sta/Elev= 30
  4697.9 1227.40  4762.2 1224.40  4777.1 1222.52  4798.0 1221.94  4842.7 1218.81
  4935.4 1217.21  4950.3 1216.29  4956.4 1214.52  4971.3 1215.10  4977.4 1212.68
  4986.2 1213.37  4992.3 1212.39  5002.2 1212.41  5007.6 1210.40  5007.9 1209.90
  5011.6 1210.40  5016.1 1212.22  5021.5 1210.44  5030.9 1214.22  5041.5 1216.51
  5046.8 1215.02  5052.2 1216.54  5077.5 1217.21  5133.4 1223.49  5194.8 1227.42
  5275.5 1235.36  5281.4 1237.38  5286.7 1237.22  5294.1 1239.56  5296.7 1239.56
#Mann=3,-1,0
  4697.9    0.05       0  5007.6    0.05       0  5011.6    0.05       0
Bank Sta=5007.6,5011.6
Exp/Cntr=0.3,0.1

Type RM Length L Ch R = 1,5882,455,455,455
BEGIN DESCRIPTION:
LITTLE LLANO 032 9.0
END DESCRIPTION:
XS GIS Cut Line= 3
      2817005.69     10270053.13      2816944.25     10269929.00
      2816855.67     10269953.11
#Sta/Elev= 30
  4861.5 1205.61  4864.3 1205.61  4869.9 1205.18  4875.5 1205.30  4883.8 1205.29
  4892.4 1204.96  4897.9 1205.27  4914.8 1204.78  4920.4 1205.16  4937.2 1204.73
  4942.8 1203.32  4950.8 1204.04  4959.7 1201.66  4965.2 1198.00  4973.1 1195.46
  4980.1 1194.41  4980.3 1193.91  4983.8 1193.91  4984.1 1194.41  4987.7 1200.17
  4994.9 1201.20  5000.0 1201.20  5008.9 1203.55  5029.6 1204.65  5034.7 1204.84
  5040.0 1205.38  5060.7 1205.74  5069.3 1206.14  5089.2 1207.65  5091.8 1207.65
#Mann=3,-1,0
  4861.5    0.05       0  4980.1    0.05       0  4984.1    0.05       0
Bank Sta=4980.1,4984.1
Exp/Cntr=0.3,0.1

Type RM Length L Ch R = 1,5427,491,491,491
BEGIN DESCRIPTION:
LITTLE LLANO 032 8.0
END DESCRIPTION:
XS GIS Cut Line= 3
      2817205.70     10269703.15      2817106.75     10269516.00
      2816905.66     10269453.10
#Sta/Elev= 30
  4788.3 1195.71  4833.6 1195.86  4840.5 1195.19  4884.6 1194.12  4912.8 1194.69
  4922.9 1193.78  4935.4 1190.05  4944.9 1188.01  4950.6 1185.37  4958.0 1187.51
  4966.9 1187.01  4972.6 1183.90  4988.9 1183.94  4992.6 1182.70  4992.8 1182.20
  4996.3 1182.20  4996.6 1182.70  5003.2 1182.98  5011.6 1188.03  5021.6 1191.89
  5032.5 1193.47  5084.9 1197.21  5116.4 1200.62  5129.5 1202.39  5147.8 1205.80
  5162.0 1208.75  5168.8 1210.92  5194.4 1214.55  5208.1 1217.30  5210.7 1217.30
#Mann=3,-1,0
  4788.3    0.05       0  4992.6    0.03       0  4996.6    0.05       0
Bank Sta=4992.6,4996.6
Exp/Cntr=0.3,0.1

Type RM Length L Ch R = 1,4936,473,473,473
BEGIN DESCRIPTION:
LITTLE LLANO 032 7.0
END DESCRIPTION:
XS GIS Cut Line= 3
      2817605.68     10269353.11      2817281.75     10269072.00
      2817055.66     10269153.12
#Sta/Elev= 30
  4571.1 1203.46  4621.0 1195.49  4663.7 1190.81  4719.7 1186.39  4727.3 1184.85
  4748.2 1184.28  4762.4 1182.58  4811.8 1182.27  4868.8 1180.19  4889.7 1181.35
  4918.2 1180.33  4940.1 1181.14  4960.9 1178.75  4975.2 1173.55  4981.8 1174.43
  4989.4 1173.06  4995.3 1175.42  5000.0 1175.42  5004.4 1172.58  5004.7 1172.08
  5008.4 1172.58  5020.2 1173.68  5027.7 1178.01  5045.7 1181.85  5137.9 1187.52
  5168.6 1191.39  5194.1 1196.99  5199.4 1196.64  5224.8 1200.38  5240.2 1201.35
#Mann=3,-1,0
  4571.1    0.05       0  5004.4    0.05       0  5008.4    0.05       0
Bank Sta=5004.4,5008.4
Exp/Cntr=0.3,0.1

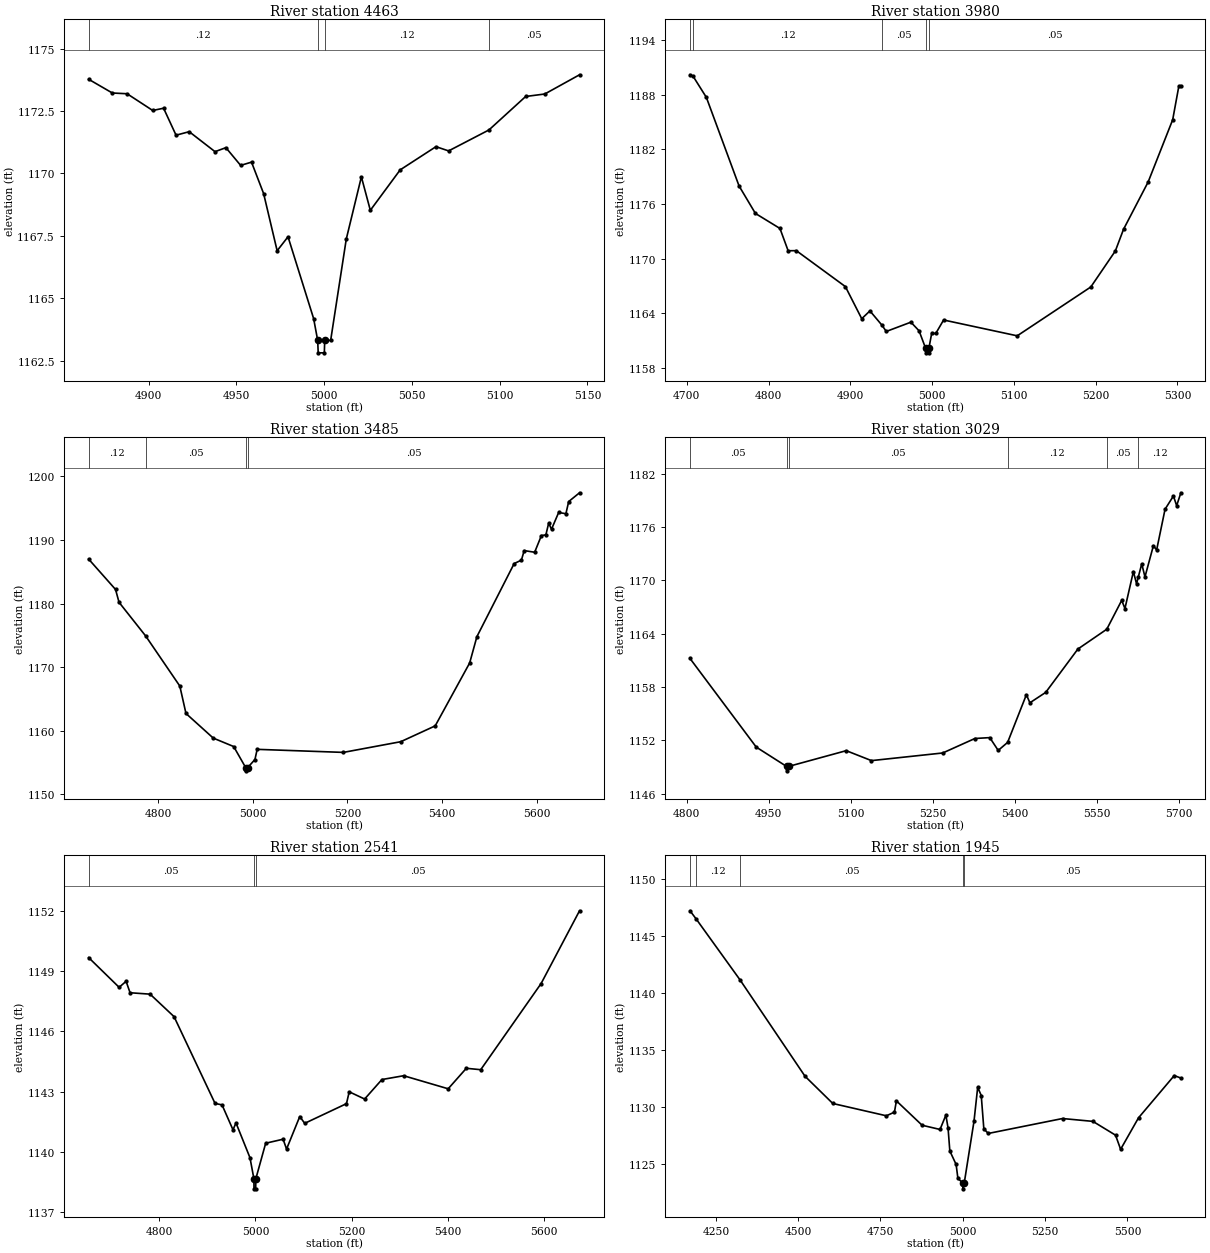
Type RM Length L Ch R = 1,4463,483,483,483
BEGIN DESCRIPTION:
LITTLE LLANO 032 6.0
END DESCRIPTION:
XS GIS Cut Line= 3
      2817455.67     10268703.10      2817348.00     10268623.00
      2817205.65     10268653.12
#Sta/Elev= 30
  4865.8 1173.77  4879.3 1173.22  4887.7 1173.19  4902.3 1172.52  4908.5 1172.61
  4915.6 1171.53  4923.1 1171.67  4937.8 1170.87  4944.0 1171.03  4952.4 1170.32
  4958.6 1170.45  4965.5 1169.19  4973.2 1166.90  4979.4 1167.46  4994.0 1164.18
  4996.3 1163.31  4996.6 1162.81  5000.1 1162.81  5000.3 1163.31  5003.7 1163.31
  5012.6 1167.37  5021.2 1169.86  5026.3 1168.52  5043.3 1170.14  5063.7 1171.07
  5070.9 1170.90  5093.9 1171.74  5114.8 1173.08  5125.7 1173.18  5145.5 1173.95
#Mann=4,-1,0
  4865.8    0.12       0  4996.3    0.07       0  5000.3    0.12       0
  5093.9    0.05       0
Bank Sta=4996.3,5000.3
Exp/Cntr=0.3,0.1

Type RM Length L Ch R = 1,3980,495,495,495
BEGIN DESCRIPTION:
LITTLE LLANO 032 5.0
END DESCRIPTION:
XS GIS Cut Line= 3
      2817605.64     10268153.11      2817309.75     10268145.00
      2817005.66     10268153.11
#Sta/Elev= 30
  4704.0 1190.21  4707.7 1190.06  4724.0 1187.73  4764.0 1177.99  4784.0 1174.97
  4814.0 1173.32  4824.0 1170.87  4834.0 1170.88  4894.0 1166.93  4914.0 1163.40
  4924.0 1164.26  4938.7 1162.69  4944.0 1162.00  4974.1 1163.02  4984.1 1162.07
  4992.1 1160.15  4992.3 1159.65  4995.8 1159.65  4996.1 1160.15  4999.5 1161.78
  5004.5 1161.78  5014.1 1163.26  5104.1 1161.52  5194.1 1166.89  5224.1 1170.85
  5234.1 1173.23  5264.2 1178.43  5294.2 1185.27  5301.7 1188.95  5304.2 1188.95
#Mann=5,-1,0
  4704.0    0.05       0  4707.7    0.12       0  4938.7    0.05       0
  4992.1    0.05       0  4996.1    0.05       0
Bank Sta=4992.1,4996.1
Exp/Cntr=0.3,0.1

Type RM Length L Ch R = 1,3485,456,456,456
BEGIN DESCRIPTION:
LITTLE LLANO 032 4.0
END DESCRIPTION:
XS GIS Cut Line= 3
      2817655.71     10267953.15      2817438.25     10267683.00
      2816855.68     10268053.12
#Sta/Elev= 30
  4653.2 1187.00  4710.0 1182.23  4717.4 1180.21  4773.5 1174.93  4845.8 1167.04
  4858.8 1162.73  4916.4 1158.86  4959.6 1157.53  4985.0 1154.21  4985.3 1153.71
  4989.0 1154.21  5004.5 1155.49  5009.2 1157.09  5191.3 1156.61  5312.5 1158.29
  5385.3 1160.78  5458.1 1170.67  5473.4 1174.81  5552.1 1186.30  5567.4 1186.84
  5573.3 1188.34  5595.4 1188.08  5609.7 1190.71  5619.1 1190.81  5625.0 1192.65
  5631.0 1191.70  5646.1 1194.33  5661.4 1194.14  5667.3 1196.05  5690.2 1197.43
#Mann=4,-1,0
  4653.2    0.12       0  4773.5    0.05       0  4985.0    0.03       0
  4989.0    0.05       0
Bank Sta=4985,4989
Exp/Cntr=0.3,0.1

Type RM Length L Ch R = 1,3029,488,488,488
BEGIN DESCRIPTION:
LITTLE LLANO 032 3.0
END DESCRIPTION:
XS GIS Cut Line= 3
      2817605.71     10267353.13      2817453.50     10267233.00
      2816855.69     10267603.11
#Sta/Elev= 30
  4806.1 1161.21  4927.2 1151.23  4982.5 1149.06  4982.7 1148.56  4986.5 1149.06
  5091.6 1150.83  5137.7 1149.71  5267.9 1150.57  5326.7 1152.20  5353.9 1152.30
  5369.3 1150.86  5386.5 1151.76  5420.8 1157.13  5427.2 1156.22  5456.1 1157.39
  5514.9 1162.27  5567.7 1164.50  5595.0 1167.75  5600.9 1166.83  5616.3 1170.99
  5622.1 1169.62  5625.2 1170.35  5631.6 1171.86  5637.5 1170.39  5652.9 1173.91
  5658.8 1173.42  5674.2 1178.01  5689.5 1179.50  5695.4 1178.41  5703.1 1179.86
#Mann=6,-1,0
  4806.1    0.05       0  4982.5    0.05       0  4986.5    0.05       0
  5386.5    0.12       0  5567.7    0.05       0  5625.2    0.12       0
Bank Sta=4982.5,4986.5
Exp/Cntr=0.3,0.1

Type RM Length L Ch R = 1,2541,596,596,596
BEGIN DESCRIPTION:
LITTLE LLANO 032 2.0
END DESCRIPTION:
XS GIS Cut Line= 3
      2817755.68     10267053.11      2817546.00     10266776.00
      2816955.67     10267103.12
#Sta/Elev= 30
  4652.5 1149.67  4716.0 1148.19  4730.5 1148.49  4738.8 1147.92  4780.5 1147.85
  4830.4 1146.73  4915.8 1142.41  4930.3 1142.34  4953.1 1141.10  4959.4 1141.44
  4988.5 1139.71  4996.7 1138.66  4996.9 1138.16  5000.4 1138.16  5000.7 1138.66
  5021.2 1140.43  5057.5 1140.63  5064.7 1140.14  5092.2 1141.76  5102.5 1141.42
  5189.5 1142.40  5195.2 1142.99  5227.3 1142.63  5263.3 1143.60  5308.6 1143.79
  5401.3 1143.14  5439.1 1144.16  5469.1 1144.09  5594.9 1148.38  5674.9 1152.00
#Mann=3,-1,0
  4652.5    0.05       0  4996.7    0.05       0  5000.7    0.05       0
Bank Sta=4996.7,5000.7
Exp/Cntr=0.3,0.1

Type RM Length L Ch R = 1,1945,558,558,558
BEGIN DESCRIPTION:
Mapping XS e157c54c
END DESCRIPTION:
XS GIS Cut Line= 2
      2818529.72     10266543.81      2817140.83     10266001.27
#Sta/Elev= 30
  4171.4 1147.23  4190.7 1146.49  4323.8 1141.15  4520.8 1132.71  4605.2 1130.32
  4767.9 1129.24  4792.4 1129.56  4798.4 1130.55  4876.5 1128.41  4930.9 1128.04
  4948.7 1129.30  4955.3 1128.17  4960.7 1126.15  4979.8 1124.97  4985.2 1123.75
  5000.4 1123.33  5000.6 1122.83  5004.4 1123.33  5034.1 1128.76  5045.3 1131.74
  5056.1 1131.02  5064.0 1128.09  5077.5 1127.69  5303.0 1129.00  5395.3 1128.75
  5464.0 1127.54  5479.5 1126.30  5533.8 1129.06  5642.4 1132.77  5662.5 1132.55
#Mann=5,-1,0
  4171.4    0.05       0  4190.7    0.12       0  4323.8    0.05       0
  5000.4    0.03       0  5004.4    0.05       0
Bank Sta=5000.4,5004.4
Exp/Cntr=0.3,0.1

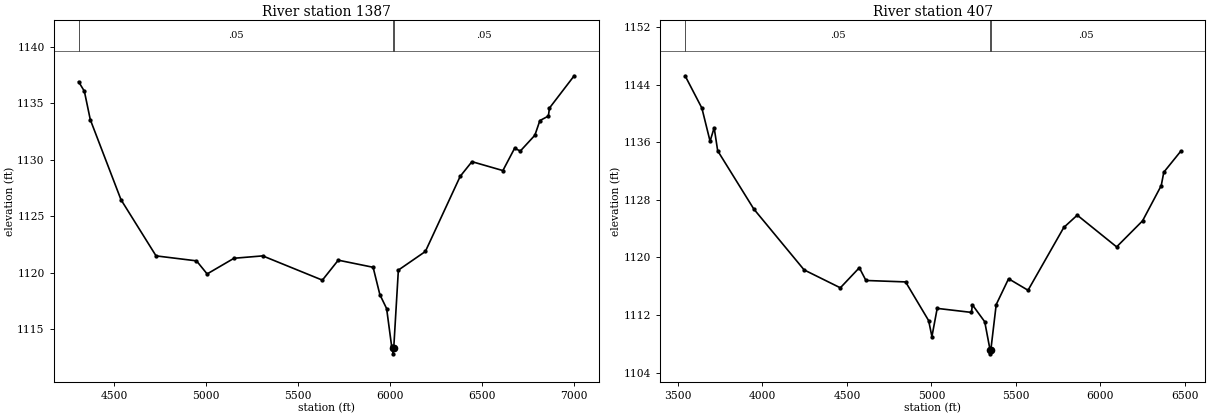
Type RM Length L Ch R = 1,1387,980,980,980
BEGIN DESCRIPTION:
Mapping XS 5a6e9bdf
END DESCRIPTION:
XS GIS Cut Line= 4
      2818466.36     10266362.04      2818320.52     10265997.46
      2817794.48     10265690.16      2816910.22     10264243.85
#Sta/Elev= 30
  4306.2 1136.91  4337.4 1136.07  4369.7 1133.55  4536.7 1126.46  4727.6 1121.48
  4947.7 1121.04  5005.6 1119.88  5151.9 1121.27  5308.1 1121.48  5632.8 1119.33
  5719.3 1121.10  5909.0 1120.47  5945.7 1118.05  5982.5 1116.81  6009.6 1113.50
  6017.2 1113.30  6017.5 1112.80  6021.2 1113.30  6046.4 1120.22  6193.4 1121.87
  6383.0 1128.53  6446.9 1129.83  6615.3 1129.04  6679.2 1131.02  6710.1 1130.77
  6789.4 1132.17  6816.6 1133.47  6862.9 1133.87  6868.8 1134.58  7003.3 1137.44
#Mann=3,-1,0
  4306.2    0.05       0  6017.2    0.03       0  6021.2    0.05       0
Bank Sta=6017.2,6021.2
Exp/Cntr=0.3,0.1

Type RM Length L Ch R = 1,407,0,0,0
BEGIN DESCRIPTION:
LITTLE LLANO 032 1.0
END DESCRIPTION:
XS GIS Cut Line= 3
      2818801.31     10266448.66      2818280.60     10264604.85
      2817410.29     10264080.10
#Sta/Elev= 30
  3542.0 1145.26  3641.3 1140.77  3689.8 1136.16  3714.0 1138.04  3734.8 1134.83
  3948.4 1126.74  4246.3 1118.27  4460.6 1115.78  4572.9 1118.57  4612.1 1116.80
  4846.7 1116.60  4983.1 1111.22  5002.5 1109.00  5033.7 1112.92  5236.6 1112.36
  5241.8 1113.42  5315.0 1111.06  5346.9 1107.10  5347.2 1106.60  5350.9 1107.10
  5382.9 1113.45  5456.1 1117.04  5571.2 1115.44  5782.8 1124.17  5862.4 1125.88
  6095.4 1121.47  6248.8 1125.09  6359.4 1129.99  6374.5 1131.85  6474.2 1134.75
#Mann=3,-1,0
  3542.0    0.05       0  5346.9    0.05       0  5350.9    0.05       0
Bank Sta=5346.9,5350.9
Exp/Cntr=0.3,0.1

Chan Stop Cuts=-1