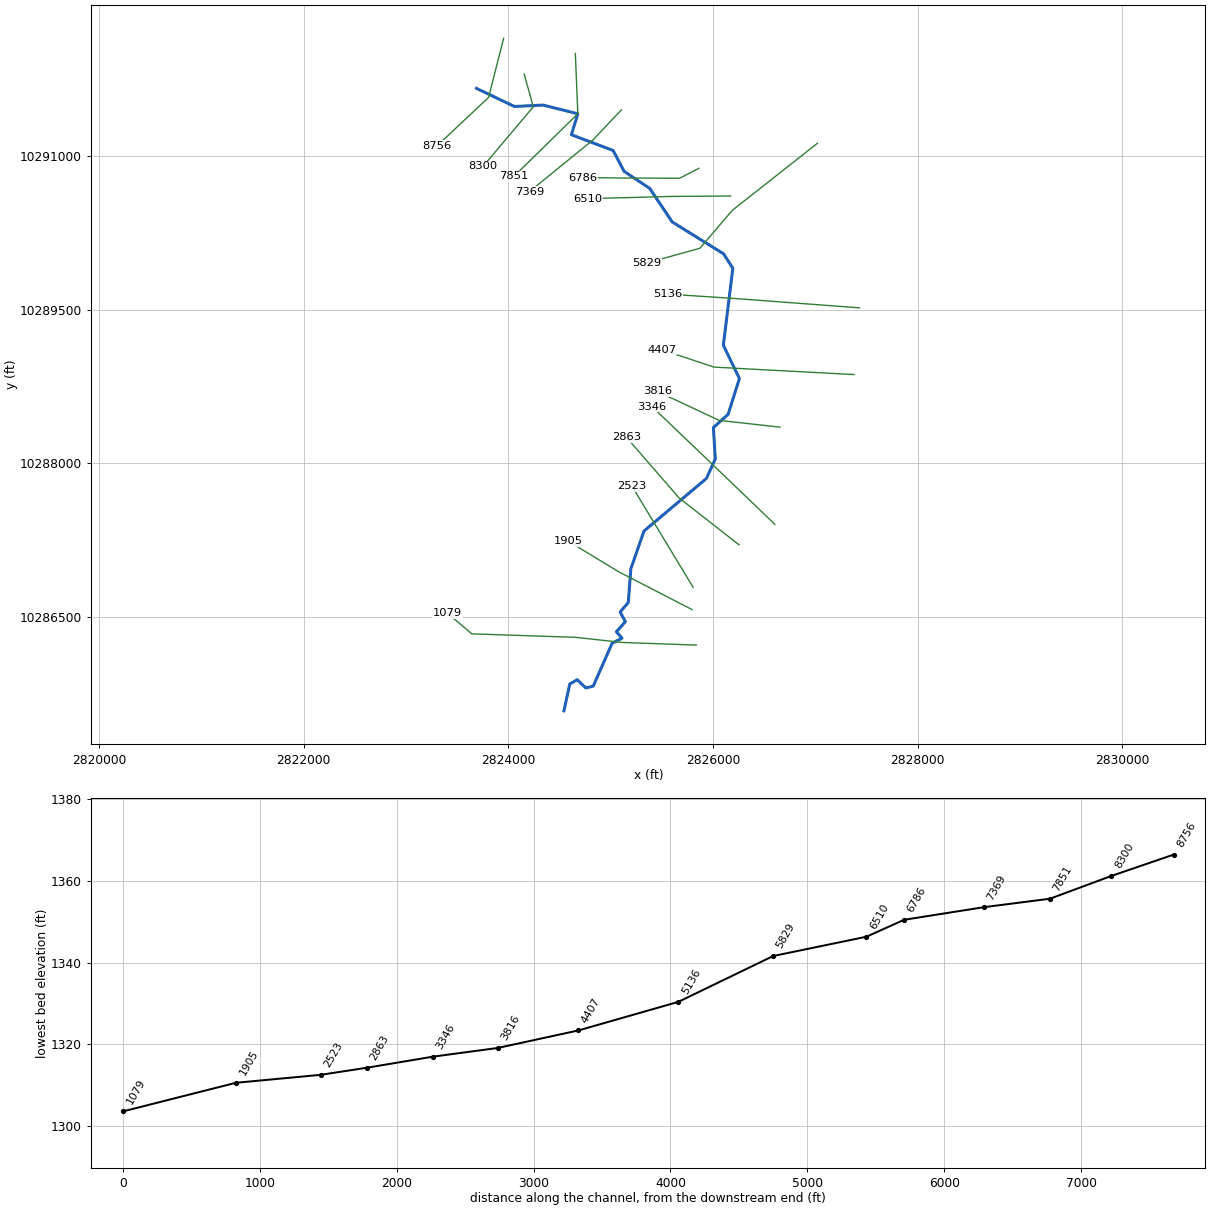
--- LITTLE LLANO 034.prj (project) ---

Proj Title=LITTLE LLANO 034 Base Level Engineering
Current Plan=p01
Default Exp/Contr=0.3,0.1
English Units
Geom File=g01
Flow File=f01
Plan File=p01
Y Axis Title=Elevation
X Axis Title(PF)=Main Channel Distance
X Axis Title(XS)=Station
BEGIN DESCRIPTION:
LITTLE LLANO 034
END DESCRIPTION:
DSS Export Rating Curves= 0
DSS Export Rating Curve Sorted= 0
DSS Export Volume Flow Curves= 0
DXF OffsetX= 0
DXF OffsetY= 0
DXF ScaleX= 1
DXF ScaleY= 10

--- LITTLE LLANO 034.p01 (plan) ---

Plan Title=Multiple Run
Short Identifier=Multiple
Geom File=g01
Flow File=f01
Subcritical Flow
K Sum by GR= 0
Std Step Tol= 0.01
Critical Tol= 0.01
Num of Std Step Trials= 20
Max Error Tol= 0.3
Flow Tol Ratio= 0.001
Split Flow NTrial= 30
Split Flow Tol= 0.02
Split Flow Ratio= 0.02
Log Output Level= 0
Friction Slope Method= 1
Unsteady Friction Slope Method= 2
Unsteady Bridges Friction Slope Method= 1
Parabolic Critical Depth
Global Vel Dist=  1 , 1 , 1
Global Log Level= 0
CheckData=True
Encroach Param= -1, 0, 0, 0
BEGIN DESCRIPTION:
Multiple Run
END DESCRIPTION:

--- LITTLE LLANO 034.f01 (steady flow) ---

Flow Title=Multiple
Number of Profiles=7
Profile Names=10-year,25-year,50-year,1pct_min,100-year,1pct_plu,500-year
River Rch & RM= LITTLE LLANO 034,Reach-1,8756
     420     679    1145     887    1570    2777    2228
Boundary for River Rch & Prof#=LITTLE LLANO 034,Reach-1,1
Up Type=0
Dn Type=3
Dn Slope=0.005
Boundary for River Rch & Prof#=LITTLE LLANO 034,Reach-1,2
Up Type=0
Dn Type=3
Dn Slope=0.005
Boundary for River Rch & Prof#=LITTLE LLANO 034,Reach-1,3
Up Type=0
Dn Type=3
Dn Slope=0.005
Boundary for River Rch & Prof#=LITTLE LLANO 034,Reach-1,4
Up Type=0
Dn Type=3
Dn Slope=0.005
Boundary for River Rch & Prof#=LITTLE LLANO 034,Reach-1,5
Up Type=0
Dn Type=3
Dn Slope=0.005
Boundary for River Rch & Prof#=LITTLE LLANO 034,Reach-1,6
Up Type=0
Dn Type=3
Dn Slope=0.005
Boundary for River Rch & Prof#=LITTLE LLANO 034,Reach-1,7
Up Type=0
Dn Type=3
Dn Slope=0.005

--- LITTLE LLANO 034.g01 (geometry) ---

Geom Title=Existing Conditions
Program Version=4.10

River Reach=LITTLE LLANO 034,Reach-1
Reach XY= 30
        2823690.       10291663.      2824060.75       10291486.
      2824340.75       10291500.      2824680.25       10291415.
      2824617.25       10291210.       2825025.5       10291056.
       2825132.5       10290852.      2825383.25       10290685.
      2825602.25       10290358.        2826105.       10290046.
        2826195.       10289905.      2826102.25       10289153.
      2826259.25       10288828.      2826148.75       10288478.
        2826005.       10288349.      2826023.75       10288042.
      2825936.25       10287851.      2825326.75       10287338.
      2825198.25       10286969.       2825173.5       10286640.
      2825093.75       10286547.      2825144.75       10286453.
      2825056.75       10286353.      2825112.25       10286291.
        2825015.       10286241.        2824831.       10285823.
       2824759.5       10285804.        2824674.       10285885.
      2824601.75       10285844.      2824544.25       10285581.

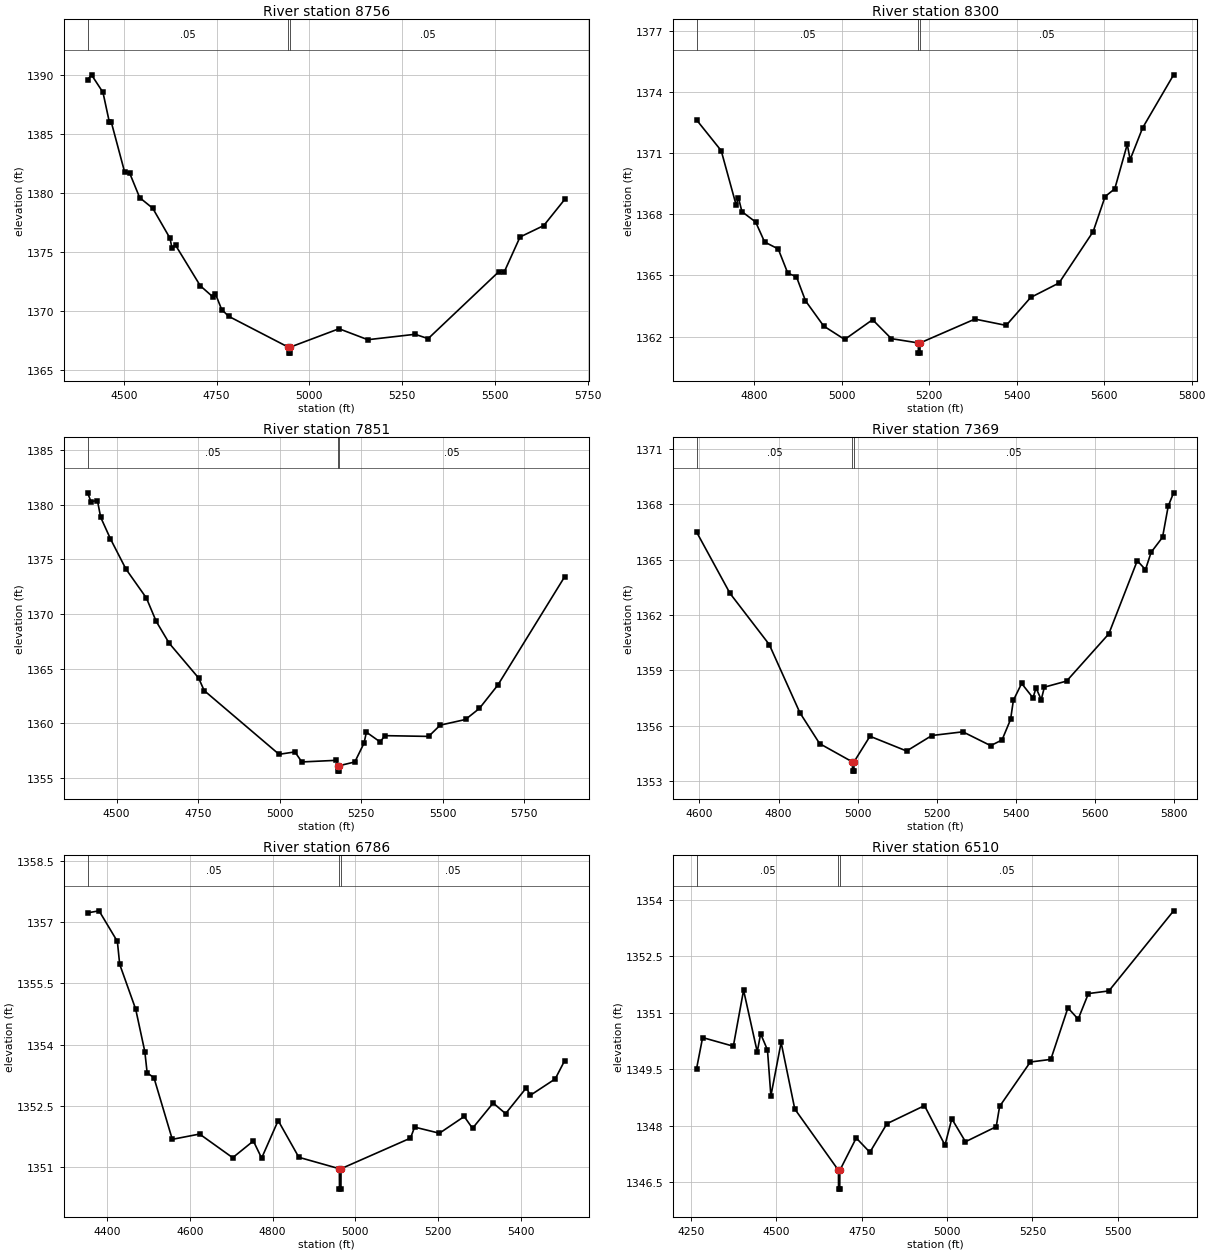
Type RM Length L Ch R = 1 ,8756    ,456,456,456
BEGIN DESCRIPTION:
LITTLE LLANO 034 15.0
END DESCRIPTION:
XS GIS Cut Line= 3
      2823955.69     10292153.14       2823807.5       10291574.
      2823305.65     10291103.08
#Sta/Elev= 30
  4402.2 1389.64  4412.6 1390.05  4443.5 1388.56  4460.9 1386.01    4466 1386.03
  4501.7 1381.82  4515.8 1381.68  4542.5 1379.62  4577.7 1378.72  4624.1 1376.18
  4629.3 1375.38  4639.6 1375.56  4705.8 1372.14  4741.4 1371.15  4746.6 1371.46
  4763.5 1370.12  4782.2 1369.55  4943.5 1366.92  4943.7 1366.42  4947.2 1366.42
  4947.5 1366.92  5079.8 1368.49  5157.5 1367.56  5284.9 1368.02  5320.1 1367.65
  5511.1 1373.35  5525.3 1373.32  5567.8 1376.28  5631.7 1377.25  5688.2 1379.47
#Mann= 3 ,-1 , 0
  4402.2     .05       0  4943.5     .03       0  4947.5     .05       0
Bank Sta=4943.5,4947.5
XS Rating Curve= 0 ,0
Exp/Cntr=0.3,0.1

Type RM Length L Ch R = 1 ,8300    ,449,449,449
BEGIN DESCRIPTION:
LITTLE LLANO 034 14.0
END DESCRIPTION:
XS GIS Cut Line= 3
      2824155.69     10291803.07        2824245.       10291483.
      2823755.72     10290903.15
#Sta/Elev= 30
  4667.7 1372.63  4724.1 1371.12  4758.3 1368.45  4763.5 1368.81  4771.5 1368.13
  4802.9 1367.62  4823.4 1366.64  4854.5  1366.3  4876.4 1365.11  4896.1 1364.94
  4916.8 1363.76  4958.4 1362.52  5006.5 1361.86  5070.3 1362.83  5113.2  1361.9
  5174.9 1361.69  5175.1 1361.19  5178.6 1361.19  5178.9 1361.69  5304.3 1362.86
  5375.8 1362.55  5431.8 1363.92  5496.7 1364.63  5574.7 1367.15  5602.1 1368.87
  5624.2 1369.25  5652.7 1371.43  5659.3 1370.68  5687.9 1372.24  5758.7 1374.84
#Mann= 3 ,-1 , 0
  4667.7     .05       0  5174.9     .03       0  5178.9     .05       0
Bank Sta=5174.9,5178.9
XS Rating Curve= 0 ,0
Exp/Cntr=0.3,0.1

Type RM Length L Ch R = 1 ,7851    ,482,482,482
BEGIN DESCRIPTION:
LITTLE LLANO 034 13.0
END DESCRIPTION:
XS GIS Cut Line= 3
      2824655.69     10292003.09      2824680.25       10291415.
      2824055.65     10290803.08
#Sta/Elev= 30
  4411.4  1381.1  4421.4  1380.3  4441.4 1380.39  4451.4 1378.86  4481.4 1376.88
  4528.8 1374.12  4591.5 1371.47  4621.6 1369.33  4661.6 1367.32  4751.7 1364.14
  4768.7 1362.99  4998.4 1357.15  5047.1 1357.37  5068.2 1356.45  5174.3  1356.6
  5179.3 1356.11  5179.6 1355.61  5183.1 1355.61  5183.3 1356.11  5230.8 1356.45
  5259.1 1358.18  5266.2 1359.18  5308.6 1358.28  5322.8 1358.86  5457.1 1358.79
  5492.5 1359.82  5570.2 1360.34  5612.7 1361.35  5669.3 1363.49  5874.4 1373.42
#Mann= 3 ,-1 , 0
  4411.4     .05       0  5179.3     .03       0  5183.3     .05       0
Bank Sta=5179.3,5183.3
XS Rating Curve= 0 ,0
Exp/Cntr=0.3,0.1

Type RM Length L Ch R = 1 ,7369    ,583,583,583
BEGIN DESCRIPTION:
LITTLE LLANO 034 12.0
END DESCRIPTION:
XS GIS Cut Line= 3
      2825105.67      10291453.1        2824826.       10291157.
      2824205.67      10290653.1
#Sta/Elev= 30
  4592.7  1366.5  4677.4 1363.17  4776.6  1360.4  4854.2  1356.7    4904 1355.03
  4986.9 1354.04  4987.2 1353.54  4990.7 1353.54  4990.9 1354.04  5031.3 1355.43
    5124 1354.63  5187.9 1355.47  5266.2 1355.67  5336.6 1354.92  5365.3 1355.23
  5386.9 1356.34    5394 1357.38  5414.9 1358.29  5443.6 1357.51  5451.3 1358.05
  5464.4 1357.41  5472.4 1358.09  5528.6 1358.42  5635.4 1360.98  5707.3 1364.94
  5728.1 1364.46  5742.4  1365.4  5771.2 1366.21  5785.6  1367.9  5799.2 1368.62
#Mann= 3 ,-1 , 0
  4592.7     .05       0  4986.9     .03       0  4990.9     .05       0
Bank Sta=4986.9,4990.9
XS Rating Curve= 0 ,0
Exp/Cntr=0.3,0.1

Type RM Length L Ch R = 1 ,6786    ,276,276,276
BEGIN DESCRIPTION:
Mapping XS 77ef0d20
END DESCRIPTION:
XS GIS Cut Line= 4
      2825862.78     10290882.11      2825675.23     10290784.87
      2825117.47     10290787.28      2824732.72      10290791.5
#Sta/Elev= 30
  4352.9 1357.23  4380.5 1357.28  4424.8 1356.53  4430.4 1355.97  4469.1 1354.87
  4491.2 1353.83  4496.8 1353.31  4513.3 1353.19  4557.6 1351.68  4623.7 1351.81
  4703.7 1351.23  4753.7 1351.64  4773.7 1351.22  4813.7 1352.14  4863.7 1351.24
  4961.7 1350.96    4962 1350.46  4965.5 1350.46  4965.7 1350.96  5133.7 1351.71
  5143.7 1351.98  5203.7 1351.83  5263.7 1352.24  5283.7 1351.95  5333.7 1352.57
  5363.7 1352.31  5413.7 1352.94  5423.7 1352.76  5483.7 1353.16  5506.7 1353.61
#Mann= 3 ,-1 , 0
  4352.9     .05       0  4961.7     .03       0  4965.7     .05       0
Bank Sta=4961.7,4965.7
XS Rating Curve= 0 ,0
Exp/Cntr=0.3,0.1

Type RM Length L Ch R = 1 ,6510    ,681,681,681
BEGIN DESCRIPTION:
Mapping XS 030669e4
END DESCRIPTION:
XS GIS Cut Line= 3
      2826173.45     10290611.26      2825579.08     10290607.04
      2824776.16     10290585.34
#Sta/Elev= 30
  4265.9 1349.51  4283.7 1350.34  4373.7 1350.11  4403.7  1351.6  4443.7 1349.96
  4453.7 1350.44  4473.7 1350.01  4483.7 1348.79  4513.7 1350.21  4553.7 1348.44
  4681.7 1346.81  4681.9 1346.31  4685.4 1346.31  4685.7 1346.81  4733.7 1347.67
  4773.7 1347.29  4823.7 1348.05  4933.7 1348.53  4993.7 1347.48  5013.7 1348.18
  5053.8 1347.57  5143.8 1347.97  5153.8 1348.51  5243.8 1349.69  5303.8 1349.76
  5353.9 1351.13  5383.9 1350.83  5413.9 1351.51  5473.9 1351.58  5663.5 1353.71
#Mann= 3 ,-1 , 0
  4265.9     .05       0  4681.7     .03       0  4685.7     .05       0
Bank Sta=4681.7,4685.7
XS Rating Curve= 0 ,0
Exp/Cntr=0.3,0.1

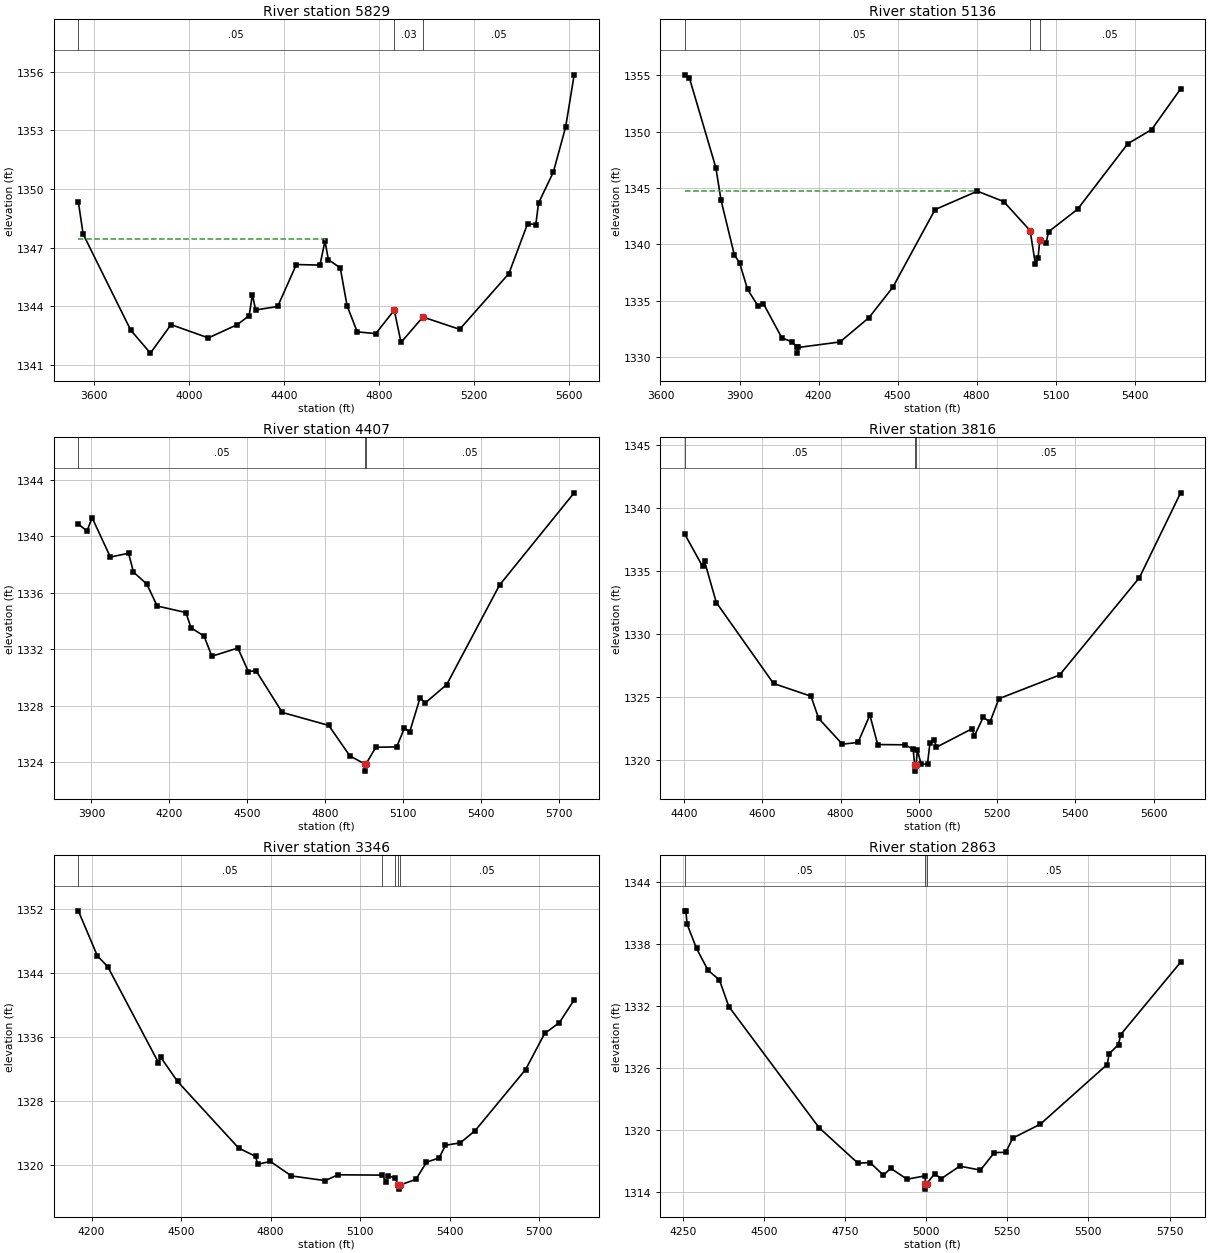
Type RM Length L Ch R = 1 ,5829    ,693,693,693
BEGIN DESCRIPTION:
Mapping XS 9981c7b6
END DESCRIPTION:
XS GIS Cut Line= 4
      2827021.54     10291126.39      2826189.12     10290470.63
      2825873.15     10290100.84      2825351.17     10289955.98
#Sta/Elev= 30
  3532.5 1349.35  3552.7 1347.69    3753 1342.77  3835.9 1341.59  3922.9 1343.05
  4080.1 1342.37  4201.9 1343.05  4251.7 1343.51  4265.6 1344.59  4278.9  1343.8
  4371.9 1343.98  4450.5 1346.13  4549.9  1346.1  4571.1 1347.34  4585.2 1346.38
  4635.5 1345.96    4664 1344.02  4706.8 1342.68  4784.8 1342.59  4862.7 1343.79
  4891.3 1342.14  4983.5 1343.44  5138.2 1342.81  5345.6 1345.67  5424.5 1348.23
  5458.8 1348.17  5470.3 1349.28  5532.5 1350.86  5584.5 1353.18  5620.3 1355.85
#Mann= 3 ,-1 , 0
  3532.5     .05       0  4862.7     .03       0  4983.5     .05       0
#XS Ineff= 2 , 0
         4572.66 1347.44
Permanent Ineff=
       F       F
Bank Sta=4862.7,4983.5
XS Rating Curve= 0 ,0
Exp/Cntr=0.3,0.1

Type RM Length L Ch R = 1 ,5136    ,729,729,729
BEGIN DESCRIPTION:
LITTLE LLANO 034 7.0
END DESCRIPTION:
XS GIS Cut Line= 3
      2827433.13     10289518.49      2826244.68     10289607.78
      2825555.67     10289653.11
#Sta/Elev= 30
  3692.3 1355.03  3709.8 1354.75  3810.1 1346.81  3830.1  1343.9  3880.3 1339.08
  3900.3 1338.37  3930.4 1336.03  3970.5 1334.53  3990.6 1334.76  4060.8 1331.72
  4100.9 1331.35    4119 1330.87  4119.2 1330.37    4123 1330.87  4281.4 1331.36
  4391.7 1333.52    4482 1336.21  4642.4 1343.09  4802.9 1344.72  4903.1  1343.8
  5003.4 1341.22  5023.4 1338.23  5033.4 1338.82  5039.9 1340.37  5063.5 1340.12
  5073.5 1341.13  5183.7 1343.13  5374.2 1348.93  5464.3 1350.17  5574.6 1353.79
#Mann= 3 , 0 , 0
  3692.3     .05       0  5003.4     .03       0  5039.9     .05       0
#XS Ineff= 2 , 0
         4797.58 1344.77
Permanent Ineff=
       F       F
Bank Sta=5003.4,5039.9
XS Rating Curve= 0 ,0
Exp/Cntr=0.3,0.1

Type RM Length L Ch R = 1 ,4407    ,591,591,591
BEGIN DESCRIPTION:
LITTLE LLANO 034 5.0
END DESCRIPTION:
XS GIS Cut Line= 3
      2827378.76     10288866.61      2826010.74     10288939.53
       2825500.5      10289109.6
#Sta/Elev= 30
  3849.6 1340.85  3882.8 1340.36  3902.7  1341.3  3972.8 1338.52  4042.9 1338.79
  4061.8 1337.46    4113 1336.61  4153.1 1335.06  4263.3  1334.6  4283.3 1333.52
  4333.4 1332.93  4363.4 1331.51  4463.5 1332.09  4503.6 1330.43  4533.6 1330.48
  4634.1 1327.54  4813.1 1326.62  4894.2 1324.47  4952.2 1323.89  4952.5 1323.39
  4956.2 1323.89  4994.3 1325.08  5074.4  1325.1  5104.5 1326.44  5124.5 1326.16
  5164.5 1328.56  5184.6 1328.21  5267.1 1329.51  5470.3 1336.54  5757.4 1343.06
#Mann= 3 ,-1 , 0
  3849.6     .05       0  4952.2     .04       0  4956.2     .05       0
Bank Sta=4952.2,4956.2
XS Rating Curve= 0 ,0
Exp/Cntr=0.3,0.1

Type RM Length L Ch R = 1 ,3816    ,470,470,470
BEGIN DESCRIPTION:
LITTLE LLANO 034 4.0
END DESCRIPTION:
XS GIS Cut Line= 3
      2826655.71     10288353.11      2826061.25       10288419.
      2825455.69     10288703.11
#Sta/Elev= 30
  4401.9  1337.9  4447.3 1335.35  4452.3 1335.76  4482.4 1332.48  4628.6 1326.05
  4724.3 1325.04    4744 1323.28  4804.4 1321.23  4844.6 1321.37  4874.8 1323.54
  4894.9  1321.2  4965.4 1321.18  4985.5 1320.81  4989.2 1319.59  4989.5 1319.09
  4993.2 1319.59    4996 1320.77  5006.1 1319.62  5022.1 1319.67  5028.2 1321.29
  5039.3 1321.55  5044.9 1320.99  5136.2 1322.46  5141.7 1321.87  5164.5 1323.37
  5181.8 1322.99  5204.6 1324.84  5359.6 1326.72  5563.5 1334.45  5668.9 1341.19
#Mann= 3 ,-1 , 0
  4401.9     .05       0  4989.2     .03       0  4993.2     .05       0
Bank Sta=4989.2,4993.2
XS Rating Curve= 0 ,0
Exp/Cntr=0.3,0.1

Type RM Length L Ch R = 1 ,3346    ,483,483,483
BEGIN DESCRIPTION:
LITTLE LLANO 034 3.0
END DESCRIPTION:
XS GIS Cut Line= 3
      2826605.66     10287403.13      2825996.75       10287988.
      2825405.72     10288553.08
#Sta/Elev= 30
  4155.7 1351.74  4219.3 1346.13  4254.6 1344.74  4424.4 1332.77  4431.6 1333.47
  4488.2 1330.43  4693.3  1322.1  4749.9 1321.07  4756.8 1320.08  4799.2 1320.44
    4870 1318.63  4983.2 1318.04  5025.7 1318.77  5174.5 1318.73  5188.3 1317.81
  5195.2 1318.64  5216.9 1318.38  5228.7 1317.48    5229 1316.98  5232.7 1317.48
  5287.3  1318.2  5322.6 1320.34    5365 1320.88  5386.4 1322.46  5435.8 1322.76
  5485.5 1324.27    5655 1331.92  5718.8 1336.42  5768.2 1337.78  5817.7 1340.62
#Mann= 5 ,-1 , 0
  4155.7     .05       0  5174.5     .12       0  5216.9     .05       0
  5228.7     .03       0  5232.7     .05       0
Bank Sta=5228.7,5232.7
XS Rating Curve= 0 ,0
Exp/Cntr=0.3,0.1

Type RM Length L Ch R = 1 ,2863    ,340,340,340
BEGIN DESCRIPTION:
LITTLE LLANO 034 2.0
END DESCRIPTION:
XS GIS Cut Line= 3
      2826255.66     10287203.13      2825669.75       10287661.
       2825155.7     10288253.09
#Sta/Elev= 30
  4256.4 1341.25  4259.5 1341.25  4263.6 1339.95  4292.5 1337.61  4327.8 1335.49
  4363.1 1334.55    4392 1331.97  4669.7 1320.24    4790 1316.78    4827 1316.85
  4868.6 1315.62  4890.9 1316.29    4941 1315.23  4997.1 1315.56  4997.4 1314.77
  4997.7 1314.27  5001.4 1314.77  5025.9 1315.76  5046.7 1315.29  5103.7  1316.5
  5167.3 1316.11  5210.1 1317.81  5245.2 1317.84  5267.1 1319.22  5351.6 1320.56
  5557.7 1326.35  5564.3 1327.41  5592.8 1328.28  5599.4 1329.25  5784.1 1336.27
#Mann= 3 ,-1 , 0
  4256.4     .05       0  4997.4     .03       0  5001.4     .05       0
Bank Sta=4997.4,5001.4
XS Rating Curve= 0 ,0
Exp/Cntr=0.3,0.1

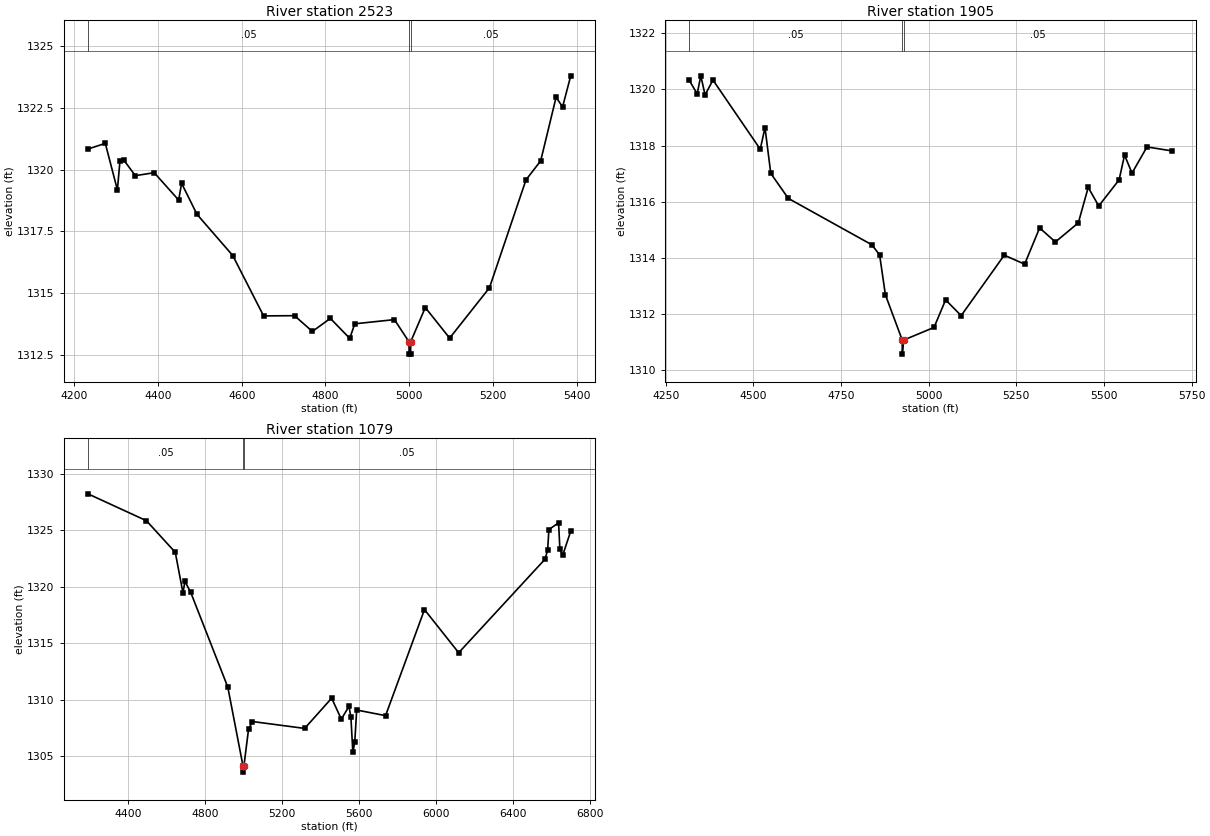
Type RM Length L Ch R = 1 ,2523    ,618,618,618
BEGIN DESCRIPTION:
Mapping XS d2bf7c00
END DESCRIPTION:
XS GIS Cut Line= 2
      2825806.93     10286787.62      2825210.43     10287774.56
#Sta/Elev= 30
  4232.7 1320.84  4274.2 1321.07  4303.1 1319.18  4309.2 1320.36  4318.6 1320.39
  4345.8 1319.76    4391 1319.88  4449.4 1318.77  4456.4 1319.45  4493.2 1318.19
  4578.6 1316.52  4652.3 1314.07  4726.1 1314.08  4768.8 1313.44  4811.7 1313.97
    4858 1313.16  4870.1 1313.75  4964.7 1313.92  4999.6 1313.02  4999.9 1312.52
  5003.4 1312.52  5003.6 1313.02  5038.5 1314.41  5096.7 1313.17  5191.7 1315.21
    5279 1319.59  5314.1 1320.36  5350.9 1322.94  5366.4 1322.55  5385.9 1323.81
#Mann= 3 ,-1 , 0
  4232.7     .05       0  4999.6     .05       0  5003.6     .05       0
Bank Sta=4999.6,5003.6
XS Rating Curve= 0 ,0
Exp/Cntr=0.3,0.1

Type RM Length L Ch R = 1 ,1905    ,826,826,826
BEGIN DESCRIPTION:
Mapping XS 9adde4b1
END DESCRIPTION:
XS GIS Cut Line= 3
       2825796.1     10286570.58      2825079.95      10286939.5
      2824591.63     10287236.05
#Sta/Elev= 30
  4316.8 1320.33  4339.8 1319.84  4350.2 1320.48  4362.3  1319.8  4384.8 1320.33
  4519.7 1317.87  4533.2 1318.64  4549.7 1317.01  4599.7 1316.12  4837.9 1314.47
  4860.1 1314.11  4876.6 1312.69  4924.6 1311.08  4924.8 1310.58  4928.6 1311.08
  5015.3 1311.53  5048.3 1312.51  5092.7 1311.95  5215.6  1314.1  5273.7 1313.78
  5316.4 1315.07  5361.4 1314.57  5426.8 1315.25    5455 1316.51    5485 1315.85
  5543.1 1316.78  5558.6 1317.66  5579.9 1317.02  5622.6 1317.95  5693.7 1317.81
#Mann= 3 ,-1 , 0
  4316.8     .05       0  4924.6     .05       0  4928.6     .05       0
Bank Sta=4924.6,4928.6
XS Rating Curve= 0 ,0
Exp/Cntr=0.3,0.1

Type RM Length L Ch R = 1 ,1079    ,0,0,0
BEGIN DESCRIPTION:
LITTLE LLANO 034 1.0
END DESCRIPTION:
XS GIS Cut Line= 5
      2825839.51     10286223.36      2825115.15     10286249.11
      2824656.77     10286299.31      2823643.69     10286333.29
      2823407.59     10286534.66
#Sta/Elev= 30
  4189.2 1328.21  4493.2 1325.83  4643.3 1323.03  4683.3 1319.43  4693.3 1320.46
  4723.4 1319.49  4916.3  1311.1  4995.8 1304.07  4996.1 1303.57  4999.8 1304.07
  5024.1 1307.36  5044.3 1308.05  5315.9 1307.44  5456.3 1310.12  5506.3 1308.26
  5546.3 1309.39  5556.3 1308.44  5566.3 1305.33  5576.3 1306.21  5586.3 1309.07
  5736.4 1308.57  5938.7 1317.96  6116.6 1314.14  6564.7 1322.41  6578.9  1323.2
  6585.5 1325.05  6635.9 1325.64  6642.6 1323.33  6656.9 1322.75  6699.1 1324.91
#Mann= 3 ,-1 , 0
  4189.2     .05       0  4995.8     .05       0  4999.8     .05       0
Bank Sta=4995.8,4999.8
XS Rating Curve= 0 ,0
Exp/Cntr=0.3,0.1

Chan Stop Cuts=-1
Use User Specified Reach Order=0
Composite Channel Slope=5