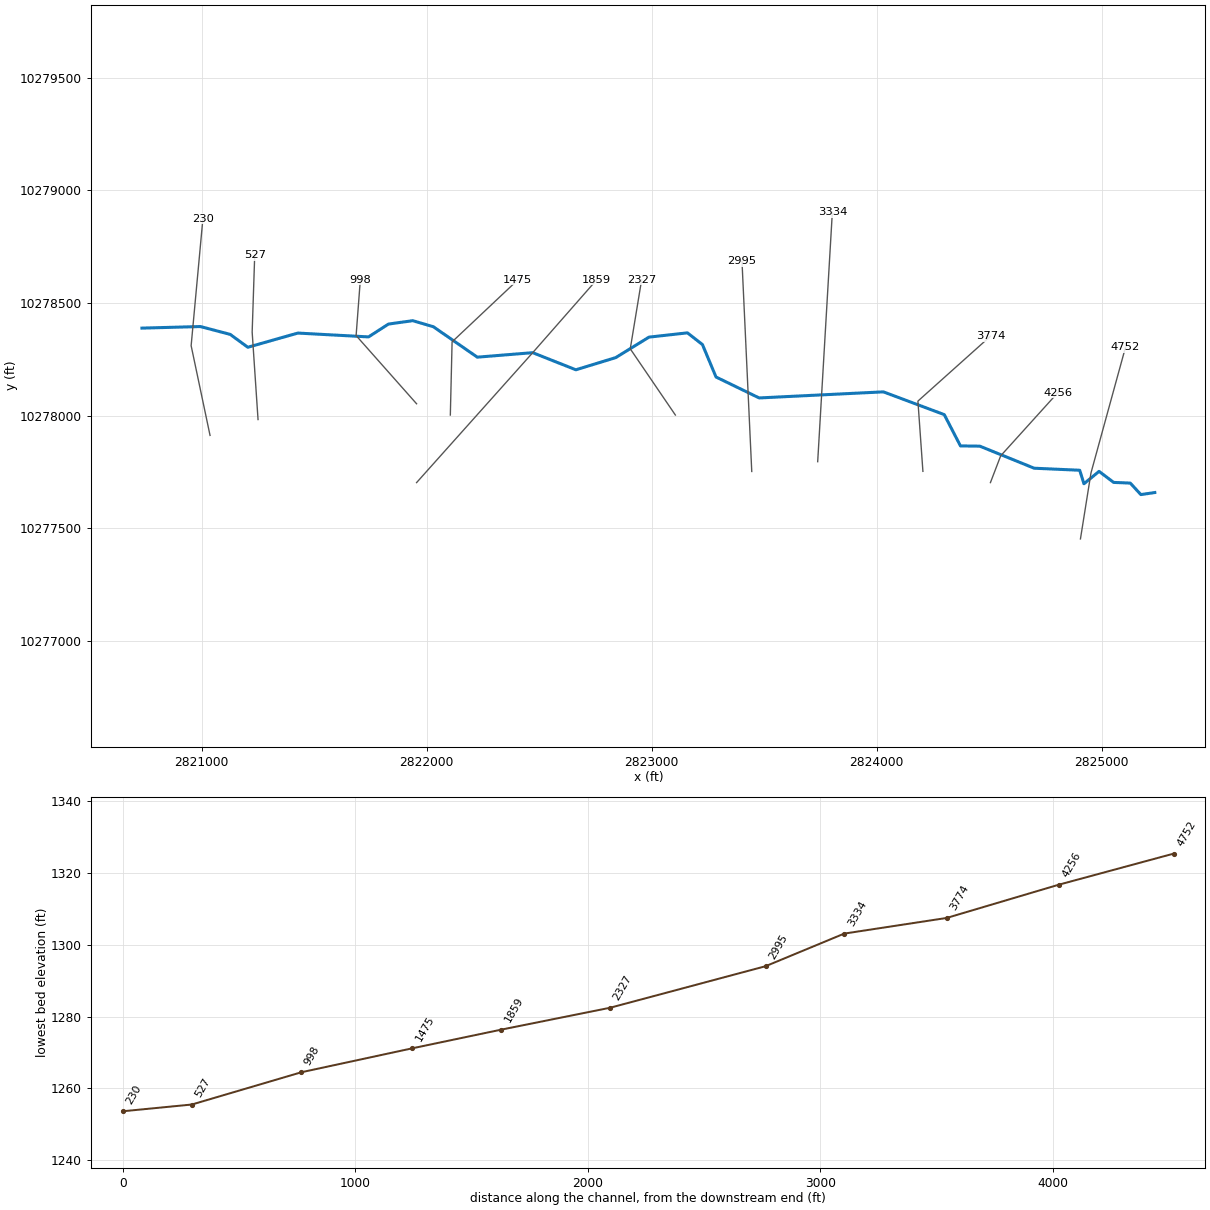
--- LITTLE LLANO 035.prj (project) ---

Proj Title=LITTLE LLANO 035 Base Level Engineering
Current Plan=p01
Default Exp/Contr=0.3,0.1
English Units
Geom File=g01
Flow File=f01
Plan File=p01
Y Axis Title=Elevation
X Axis Title(PF)=Main Channel Distance
X Axis Title(XS)=Station
BEGIN DESCRIPTION:
LITTLE LLANO 035
END DESCRIPTION:
DSS Export Rating Curves= 0
DSS Export Rating Curve Sorted= 0
DSS Export Volume Flow Curves= 0
DXF OffsetX= 0
DXF OffsetY= 0
DXF ScaleX= 1
DXF ScaleY= 10

--- LITTLE LLANO 035.p01 (plan) ---

Plan Title=Multiple Run
Short Identifier=Multiple
Geom File=g01
Flow File=f01
Subcritical Flow
K Sum by GR= 0
Std Step Tol= 0.01
Critical Tol= 0.01
Num of Std Step Trials= 20
Max Error Tol= 0.3
Flow Tol Ratio= 0.001
Split Flow NTrial= 30
Split Flow Tol= 0.02
Split Flow Ratio= 0.02
Log Output Level= 0
Friction Slope Method= 1
Unsteady Friction Slope Method= 2
Unsteady Bridges Friction Slope Method= 1
Parabolic Critical Depth
Global Vel Dist=  1 , 1 , 1
Global Log Level= 0
CheckData=True
Encroach Param= -1, 0, 0, 0
BEGIN DESCRIPTION:
Multiple Run
END DESCRIPTION:

--- LITTLE LLANO 035.f01 (steady flow) ---

Flow Title=Multiple
Number of Profiles=7
Profile Names=10-year,25-year,50-year,1pct_min,100-year,1pct_plu,500-year
River Rch & RM= LITTLE LLANO 035,Reach-1,4752
     224     349     517     401     689    1184     979
Boundary for River Rch & Prof#=LITTLE LLANO 035,Reach-1,1
Up Type=0
Dn Type=3
Dn Slope=0.005
Boundary for River Rch & Prof#=LITTLE LLANO 035,Reach-1,2
Up Type=0
Dn Type=3
Dn Slope=0.005
Boundary for River Rch & Prof#=LITTLE LLANO 035,Reach-1,3
Up Type=0
Dn Type=3
Dn Slope=0.005
Boundary for River Rch & Prof#=LITTLE LLANO 035,Reach-1,4
Up Type=0
Dn Type=3
Dn Slope=0.005
Boundary for River Rch & Prof#=LITTLE LLANO 035,Reach-1,5
Up Type=0
Dn Type=3
Dn Slope=0.005
Boundary for River Rch & Prof#=LITTLE LLANO 035,Reach-1,6
Up Type=0
Dn Type=3
Dn Slope=0.005
Boundary for River Rch & Prof#=LITTLE LLANO 035,Reach-1,7
Up Type=0
Dn Type=3
Dn Slope=0.005

--- LITTLE LLANO 035.g01 (geometry) ---

Geom Title=Existing Conditions
Program Version=4.10

River Reach=LITTLE LLANO 035,Reach-1
Reach XY= 30
        2825236.       10277659.        2825174.       10277650.
      2825127.25       10277701.      2825053.25       10277704.
       2824988.5       10277753.      2824921.25       10277698.
       2824902.5       10277758.      2824700.25       10277767.
       2824458.5       10277865.       2824372.5       10277866.
       2824300.5       10278005.        2824030.       10278106.
        2823478.       10278079.      2823286.25       10278172.
        2823226.       10278316.      2823159.25       10278368.
       2822988.5       10278349.       2822840.5       10278258.
       2822663.5       10278204.      2822471.75       10278280.
       2822225.5       10278260.       2822030.5       10278395.
      2821938.75       10278422.      2821830.75       10278407.
      2821742.25       10278350.        2821428.       10278367.
      2821205.75       10278304.      2821127.75       10278361.
        2820995.       10278396.      2820735.25       10278389.

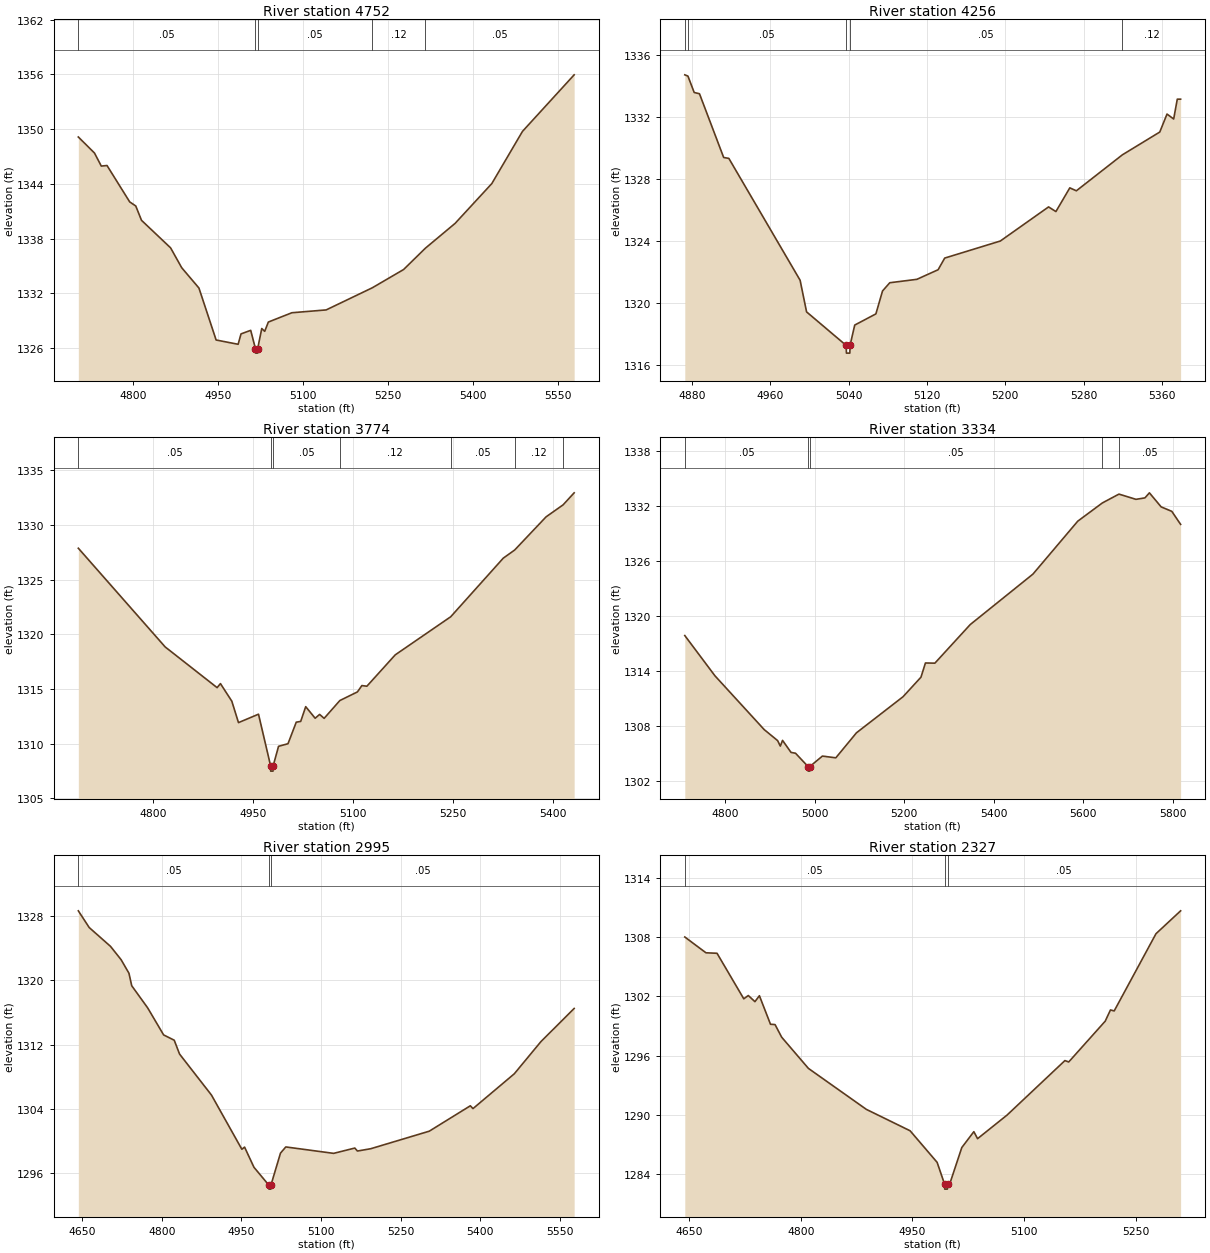
Type RM Length L Ch R = 1 ,4752    ,496,496,496
BEGIN DESCRIPTION:
LITTLE LLANO 035 10.0
END DESCRIPTION:
XS GIS Cut Line= 3
      2824905.69     10277453.12       2824952.5       10277746.
      2825105.69     10278303.12
#Sta/Elev= 30
  4703.4 1349.14  4731.9 1347.38  4743.9 1345.95    4754 1346.01    4794 1342.02
  4804.7 1341.57  4814.8    1340  4866.1 1336.98  4885.7  1334.8  4916.1 1332.57
  4946.4 1326.87  4985.2  1326.4  4990.3 1327.54  5007.4 1327.93  5015.7 1325.93
    5016 1325.43  5019.5 1325.43  5019.7 1325.93  5026.9 1328.13  5032.1 1327.82
  5038.5 1328.84    5080 1329.86  5140.5 1330.17  5221.9  1332.6    5277  1334.6
  5315.6 1336.95  5367.8 1339.66  5432.6 1344.03  5486.6 1349.75  5577.8 1355.96
#Mann= 5 ,-1 , 0
  4703.4     .05       0  5015.7     .05       0  5019.7     .05       0
  5221.9     .12       0  5315.6     .05       0
Bank Sta=5015.7,5019.7
XS Rating Curve= 0 ,0
Exp/Cntr=0.3,0.1

Type RM Length L Ch R = 1 ,4256    ,482,482,482
BEGIN DESCRIPTION:
LITTLE LLANO 035 9.0
END DESCRIPTION:
XS GIS Cut Line= 3
      2824505.69     10277703.13      2824551.25       10277822.
      2824805.71     10278103.14
#Sta/Elev= 30
  4872.7 1334.69  4875.9 1334.61  4882.3 1333.55  4887.7 1333.47  4912.4 1329.36
  4917.7  1329.3  4990.5 1321.44  4997.1  1319.4  5037.5 1317.24  5037.8 1316.74
  5041.3 1316.74  5041.5 1317.24  5046.3 1318.55  5067.9 1319.27  5074.7 1320.75
  5082.1 1321.28  5109.8  1321.5  5131.5 1322.12  5138.2 1322.87    5195 1323.97
  5244.3 1326.17  5251.8 1325.87    5266  1327.4  5272.7 1327.21  5319.7 1329.53
  5357.9    1331  5365.3 1332.16  5372.1 1331.84  5375.8 1333.12  5379.2 1333.12
#Mann= 5 ,-1 , 0
  4872.7     .12       0  4875.9     .05       0  5037.5     .05       0
  5041.5     .05       0  5319.7     .12       0
Bank Sta=5037.5,5041.5
XS Rating Curve= 0 ,0
Exp/Cntr=0.3,0.1

Type RM Length L Ch R = 1 ,3774    ,440,440,440
BEGIN DESCRIPTION:
LITTLE LLANO 035 8.0
END DESCRIPTION:
XS GIS Cut Line= 3
      2824205.69     10277753.09       2824183.5       10278065.
      2824505.67      10278353.1
#Sta/Elev= 30
  4687.3 1327.88  4817.7 1318.85  4895.8 1315.12  4900.8 1315.49  4917.9 1313.88
  4927.9 1311.92    4958 1312.69  4976.1 1307.98  4976.3 1307.48  4979.8 1307.48
  4980.1 1307.98  4988.1 1309.75  5002.3 1309.99  5014.7 1311.96  5021.4 1312.03
  5028.9 1313.38  5043.1 1312.32  5049.8 1312.67  5056.6 1312.31  5080.2 1313.94
  5106.6 1314.73  5113.3 1315.31  5120.8 1315.25  5163.4 1318.12  5246.8 1321.61
  5325.7 1326.97  5342.9 1327.72    5390 1330.75  5415.6 1331.85  5432.2 1332.95
#Mann= 7 ,-1 , 0
  4687.3     .05       0  4976.1     .05       0  4980.1     .05       0
  5080.2     .12       0  5246.8     .05       0  5342.9     .12       0
  5415.6     .05       0
Bank Sta=4976.1,4980.1
XS Rating Curve= 0 ,0
Exp/Cntr=0.3,0.1

Type RM Length L Ch R = 1 ,3334    ,339,339,339
BEGIN DESCRIPTION:
Mapping XS f89ca3ca
END DESCRIPTION:
XS GIS Cut Line= 2
      2823738.08     10277795.96      2823803.18     10278902.75
#Sta/Elev= 30
  4709.4 1317.91  4776.7 1313.53  4886.9 1307.66  4916.9 1306.46    4923 1305.86
    4928 1306.48    4947 1305.17    4957 1305.08    4985 1303.63  4985.3 1303.13
  4988.8 1303.13    4989 1303.63  5017.1 1304.77  5047.1 1304.58  5093.3 1307.31
  5197.4 1311.24  5237.5 1313.37  5247.5 1314.92  5268.6  1314.9  5347.7 1319.11
  5487.9 1324.61  5588.1 1330.38  5643.2 1332.37  5680.2 1333.33  5718.3 1332.76
  5738.3 1332.92  5748.3 1333.47  5774.5 1331.94  5798.4 1331.45  5818.1 1330.03
#Mann= 5 ,-1 , 0
  4709.4     .05       0    4985     .05       0    4989     .05       0
  5643.2     .12       0  5680.2     .05       0
Bank Sta=4985,4989
XS Rating Curve= 0 ,0
Exp/Cntr=0.3,0.1

Type RM Length L Ch R = 1 ,2995    ,668,668,668
BEGIN DESCRIPTION:
Mapping XS cdc5aa62
END DESCRIPTION:
XS GIS Cut Line= 2
      2823445.11     10277752.59       2823401.7     10278685.78
#Sta/Elev= 30
  4642.9 1328.66  4663.4 1326.58  4703.5 1324.24  4723.5 1322.58  4738.3 1320.89
  4743.5 1319.34  4773.6 1316.58  4803.6 1313.22  4823.6 1312.56  4833.6 1310.84
  4893.7 1305.74    4951 1298.99  4956.1 1299.26  4973.8 1296.75  5001.8 1294.53
  5002.1 1294.03  5005.6 1294.03  5005.8 1294.53  5023.8 1298.51  5033.8 1299.28
  5123.9 1298.48  5163.8 1299.14  5168.8 1298.77    5194 1299.06  5304.1 1301.24
  5381.5  1304.4  5386.5 1304.05  5464.3 1308.38  5514.4 1312.38  5577.1 1316.51
#Mann= 3 ,-1 , 0
  4642.9     .05       0  5001.8     .05       0  5005.8     .05       0
Bank Sta=5001.8,5005.8
XS Rating Curve= 0 ,0
Exp/Cntr=0.3,0.1

Type RM Length L Ch R = 1 ,2327    ,468,468,468
BEGIN DESCRIPTION:
LITTLE LLANO 035 5.0
END DESCRIPTION:
XS GIS Cut Line= 3
      2823105.67     10278003.14      2822905.25       10278297.
      2822955.68     10278603.07
#Sta/Elev= 30
  4644.3 1308.01  4672.7 1306.41  4687.6 1306.36  4723.5 1301.75  4729.6 1302.08
  4738.5 1301.46  4744.5 1302.06  4759.4 1299.17  4765.5 1299.14  4774.4 1297.86
  4810.3  1294.7  4888.1 1290.55  4946.9 1288.38  4983.2 1285.18  4993.2 1282.97
  4993.4 1282.47  4996.9 1282.47  4997.2 1282.97    5000 1282.97  5016.3 1286.68
  5032.5 1288.29  5037.5 1287.58  5077.1 1289.97  5154.8 1295.49  5159.9 1295.35
  5208.9 1299.48    5216 1300.62    5221 1300.52  5277.1 1308.34  5310.2 1310.66
#Mann= 3 ,-1 , 0
  4644.3     .05       0  4993.2     .03       0  4997.2     .05       0
Bank Sta=4993.2,4997.2
XS Rating Curve= 0 ,0
Exp/Cntr=0.3,0.1

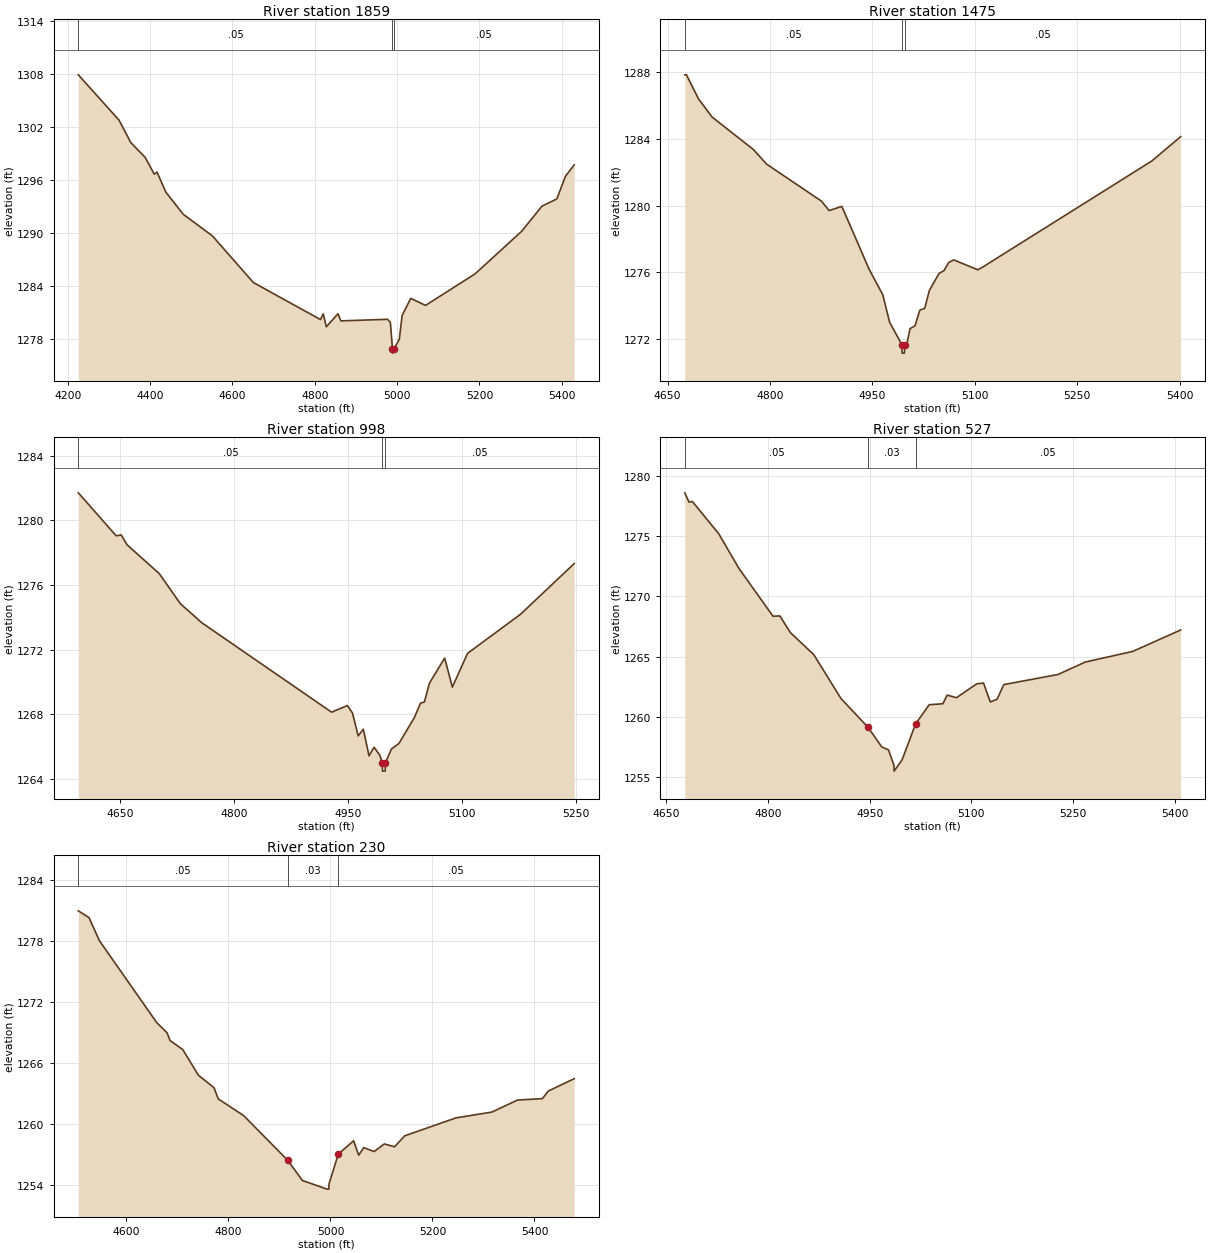
Type RM Length L Ch R = 1 ,1859    ,384,384,384
BEGIN DESCRIPTION:
LITTLE LLANO 035 4.0
END DESCRIPTION:
XS GIS Cut Line= 3
       2821955.7     10277703.13      2822471.75       10278280.
      2822755.66     10278603.08
#Sta/Elev= 30
    4226 1307.87    4325 1302.73  4353.4  1300.2  4388.6 1298.51  4410.3 1296.62
    4417 1296.86  4438.7 1294.58  4480.9 1292.08  4551.6 1289.64    4651 1284.36
    4814 1280.17  4820.7 1280.82  4828.2 1279.35  4856.6 1280.83  4863.4 1280.02
    4977  1280.2  4983.7 1279.84  4988.8 1276.87    4989 1276.37  4992.8 1276.87
  5005.4 1277.94  5012.2 1280.62  5033.1 1282.57  5069.1 1281.77  5189.6 1285.35
  5302.5 1290.16  5351.9 1293.01  5387.9 1293.82  5408.8 1296.39  5430.1 1297.68
#Mann= 3 ,-1 , 0
    4226     .05       0  4988.8     .03       0  4992.8     .05       0
Bank Sta=4988.8,4992.8
XS Rating Curve= 0 ,0
Exp/Cntr=0.3,0.1

Type RM Length L Ch R = 1 ,1475    ,477,477,477
BEGIN DESCRIPTION:
LITTLE LLANO 035 3.0
END DESCRIPTION:
XS GIS Cut Line= 3
      2822105.68     10278003.09       2822113.5       10278328.
      2822405.67      10278603.1
#Sta/Elev= 30
    4675 1287.84  4677.5 1287.84    4695 1286.41    4715 1285.31    4775 1283.38
  4795.1 1282.48  4875.1 1280.27  4886.5  1279.7  4905.1 1279.95  4945.1 1276.18
  4965.1 1274.65  4975.1    1273  4993.1 1271.65  4993.3 1271.15  4996.8 1271.15
  4997.1 1271.65    5000 1271.65    5005 1272.62  5012.3 1272.79  5019.2 1273.72
  5026.5 1273.84  5033.3 1274.91  5047.5 1275.93  5054.8  1276.1  5061.7 1276.59
    5069 1276.74  5104.1 1276.15  5111.4 1276.31    5359 1282.67  5401.3 1284.13
#Mann= 3 ,-1 , 0
    4675     .05       0  4993.1     .03       0  4997.1     .05       0
Bank Sta=4993.1,4997.1
XS Rating Curve= 0 ,0
Exp/Cntr=0.3,0.1

Type RM Length L Ch R = 1 ,998     ,471,471,471
BEGIN DESCRIPTION:
LITTLE LLANO 035 2.0
END DESCRIPTION:
XS GIS Cut Line= 3
      2821955.69      10278053.1        2821687.       10278356.
      2821705.68     10278603.09
#Sta/Elev= 30
  4595.1 1281.71  4644.9 1279.05  4651.6  1279.1  4659.1  1278.5  4701.8  1276.7
  4729.3 1274.85  4757.8 1273.66  4928.4 1268.13  4949.3 1268.54    4956 1268.07
  4963.5 1266.66  4970.2 1267.08  4977.7 1265.43  4984.4 1265.96    4992 1265.46
  4995.2 1264.98  4995.5 1264.48    4999 1264.48  4999.2 1264.98  5007.1 1265.84
  5017.2  1266.2  5037.2 1267.78  5045.5 1268.69  5050.6 1268.76  5057.3 1269.93
  5077.3 1271.48  5087.4 1269.68  5107.4 1271.77  5177.1 1274.19  5247.8 1277.33
#Mann= 3 ,-1 , 0
  4595.1     .05       0  4995.2     .03       0  4999.2     .05       0
Bank Sta=4995.2,4999.2
XS Rating Curve= 0 ,0
Exp/Cntr=0.3,0.1

Type RM Length L Ch R = 1 ,527     ,297,297,297
BEGIN DESCRIPTION:
Mapping XS a7bf4c3c
END DESCRIPTION:
XS GIS Cut Line= 3
      2821251.19      10277983.1      2821225.09     10278371.18
      2821236.44     10278713.83
#Sta/Elev= 30
    4677 1278.58  4683.3 1277.81  4688.3 1277.86  4727.1 1275.19  4757.2 1272.29
  4807.3 1268.34  4817.3 1268.37    4833 1266.98  4867.4 1265.16  4907.5 1261.52
  4947.6 1259.12  4967.7  1257.5  4977.7 1257.25  4985.7 1255.99    4986 1255.49
  4997.7 1256.42  5017.8 1259.42  5037.8    1261  5057.9 1261.08  5064.4  1261.8
  5077.9 1261.58  5107.9 1262.73  5117.9  1262.8  5127.9 1261.23  5137.9 1261.45
  5147.9 1262.67    5228 1263.51    5268 1264.54    5338 1265.42  5408.8  1267.2
#Mann= 3 , 0 , 0
    4677     .05       0  4947.6     .03       0  5017.8     .05       0
Bank Sta=4947.6,5017.8
XS Rating Curve= 0 ,0
Exp/Cntr=0.3,0.1

Type RM Length L Ch R = 1 ,230     ,0,0,0
BEGIN DESCRIPTION:
LITTLE LLANO 035 1.0
END DESCRIPTION:
XS GIS Cut Line= 3
      2821037.88     10277912.73       2820953.9     10278311.04
       2821006.1     10278873.86
#Sta/Elev= 30
  4505.6 1280.95  4526.4 1280.29  4546.9 1278.02  4659.3 1269.97  4679.7 1268.96
  4685.4 1268.21  4710.4 1267.32    4741  1264.8  4771.7 1263.57  4779.8 1262.48
  4829.6 1260.84  4916.2 1256.44  4944.9 1254.46  4993.3 1253.61  4996.8 1253.61
  4997.1 1254.11  5015.2 1257.04  5045.3 1258.36  5055.3 1256.95  5065.4 1257.69
  5085.5  1257.3  5105.6 1258.05  5125.6 1257.77  5145.7 1258.85  5246.2 1260.61
  5316.5 1261.18  5366.7 1262.36  5415.6  1262.5  5426.9 1263.24  5477.9 1264.46
#Mann= 3 , 0 , 0
  4505.6     .05       0  4916.2     .03       0  5015.2     .05       0
Bank Sta=4916.2,5015.2
XS Rating Curve= 0 ,0
Exp/Cntr=0.3,0.1

Chan Stop Cuts=-1
Use User Specified Reach Order=0
Composite Channel Slope=5