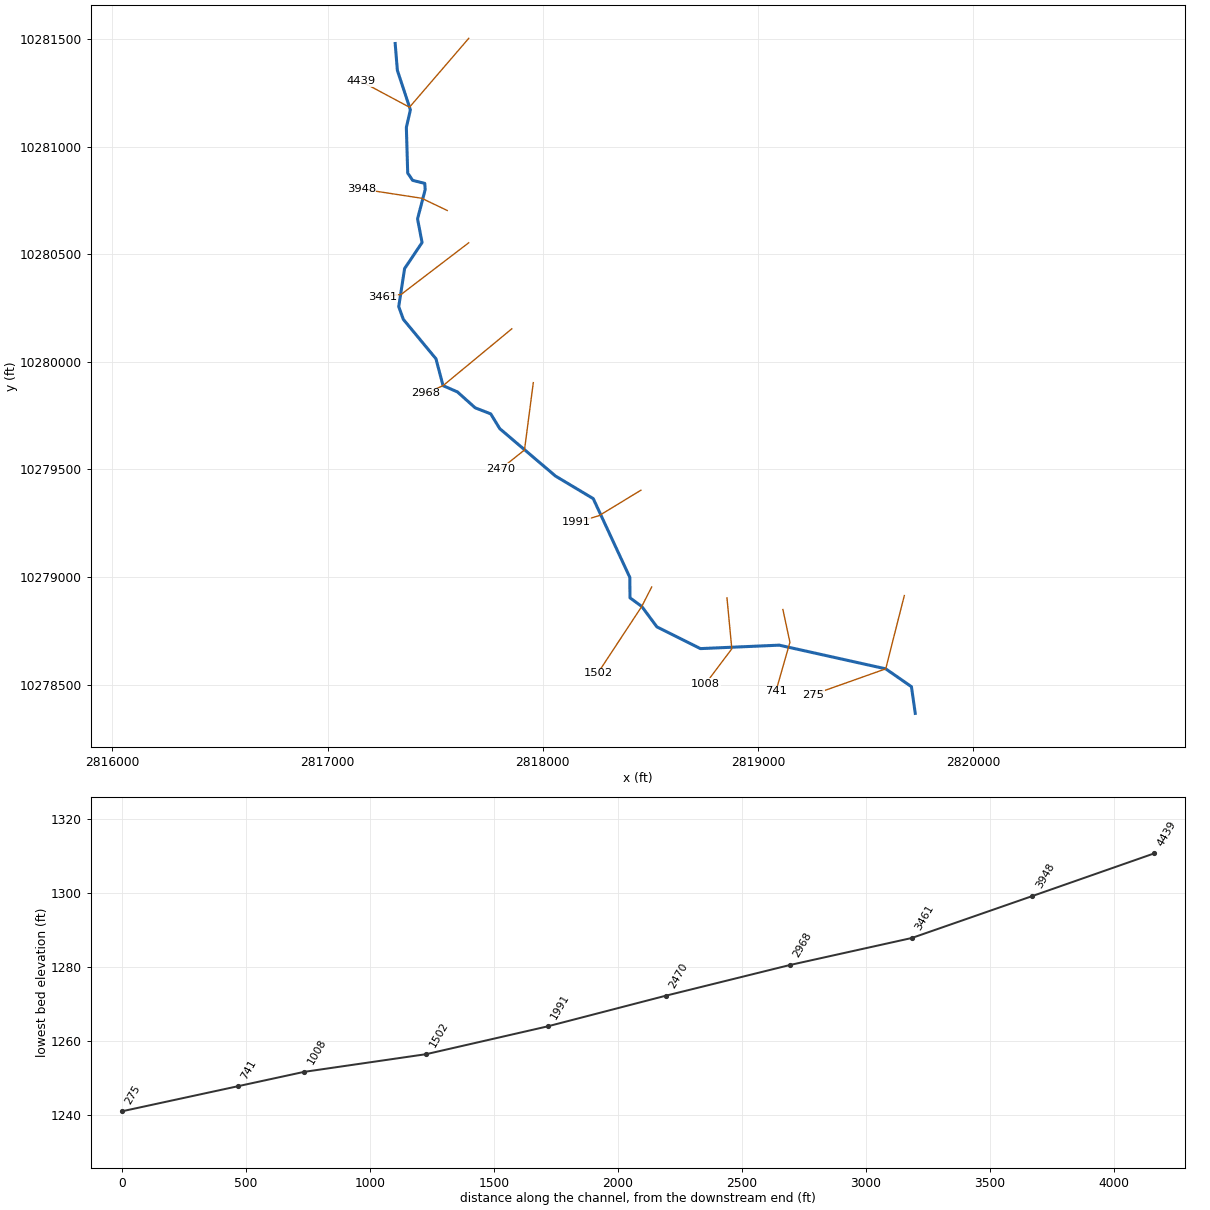
--- LITTLE LLANO 036.prj (project) ---

Proj Title=LITTLE LLANO 036 Base Level Engineering
Current Plan=p01
Default Exp/Contr=0.3,0.1
English Units
Geom File=g01
Flow File=f01
Plan File=p01
Y Axis Title=Elevation
X Axis Title(PF)=Main Channel Distance
X Axis Title(XS)=Station
BEGIN DESCRIPTION:
LITTLE LLANO 036
END DESCRIPTION:
DSS Export Rating Curves= 0
DSS Export Rating Curve Sorted= 0
DSS Export Volume Flow Curves= 0
DXF OffsetX= 0
DXF OffsetY= 0
DXF ScaleX= 1
DXF ScaleY= 10

--- LITTLE LLANO 036.p01 (plan) ---

Plan Title=Multiple Run
Short Identifier=Multiple
Geom File=g01
Flow File=f01
Subcritical Flow
K Sum by GR= 0
Std Step Tol= 0.01
Critical Tol= 0.01
Num of Std Step Trials= 20
Max Error Tol= 0.3
Flow Tol Ratio= 0.001
Split Flow NTrial= 30
Split Flow Tol= 0.02
Split Flow Ratio= 0.02
Log Output Level= 0
Friction Slope Method= 1
Unsteady Friction Slope Method= 2
Unsteady Bridges Friction Slope Method= 1
Parabolic Critical Depth
Global Vel Dist=  1 , 1 , 1
Global Log Level= 0
CheckData=True
Encroach Param= -1, 0, 0, 0
BEGIN DESCRIPTION:
Multiple Run
END DESCRIPTION:

--- LITTLE LLANO 036.f01 (steady flow) ---

Flow Title=Multiple
Number of Profiles=7
Profile Names=10-year,25-year,50-year,1pct_min,100-year,1pct_plu,500-year
River Rch & RM= LITTLE LLANO 036,Reach-1,4439
     186     287     411     324     542     907     768
River Rch & RM= LITTLE LLANO 036,Reach-1,275
     258     403     639     522     856    1404    1209
Boundary for River Rch & Prof#=LITTLE LLANO 036,Reach-1,1
Up Type=0
Dn Type=3
Dn Slope=0.005
Boundary for River Rch & Prof#=LITTLE LLANO 036,Reach-1,2
Up Type=0
Dn Type=3
Dn Slope=0.005
Boundary for River Rch & Prof#=LITTLE LLANO 036,Reach-1,3
Up Type=0
Dn Type=3
Dn Slope=0.005
Boundary for River Rch & Prof#=LITTLE LLANO 036,Reach-1,4
Up Type=0
Dn Type=3
Dn Slope=0.005
Boundary for River Rch & Prof#=LITTLE LLANO 036,Reach-1,5
Up Type=0
Dn Type=3
Dn Slope=0.005
Boundary for River Rch & Prof#=LITTLE LLANO 036,Reach-1,6
Up Type=0
Dn Type=3
Dn Slope=0.005
Boundary for River Rch & Prof#=LITTLE LLANO 036,Reach-1,7
Up Type=0
Dn Type=3
Dn Slope=0.005

--- LITTLE LLANO 036.g01 (geometry) ---

Geom Title=Existing Conditions
Program Version=4.10

River Reach=LITTLE LLANO 036,Reach-1
Reach XY= 30
      2817313.75       10281479.        2817324.       10281354.
       2817384.5       10281171.      2817365.75       10281089.
        2817372.       10280877.        2817395.       10280843.
      2817451.25       10280829.      2817453.25       10280800.
      2817417.75       10280664.      2817438.75       10280554.
       2817357.5       10280433.      2817330.25       10280256.
      2817351.75       10280197.      2817503.25       10280014.
      2817536.25       10279889.        2817603.       10279860.
       2817685.5       10279786.      2817757.75       10279758.
        2817800.       10279689.      2818058.75       10279469.
      2818234.25       10279364.      2818404.25       10278998.
        2818405.       10278903.      2818459.75       10278863.
        2818530.       10278768.       2818732.5       10278667.
       2819098.5       10278683.       2819593.5       10278573.
        2819713.       10278490.      2819730.75       10278366.

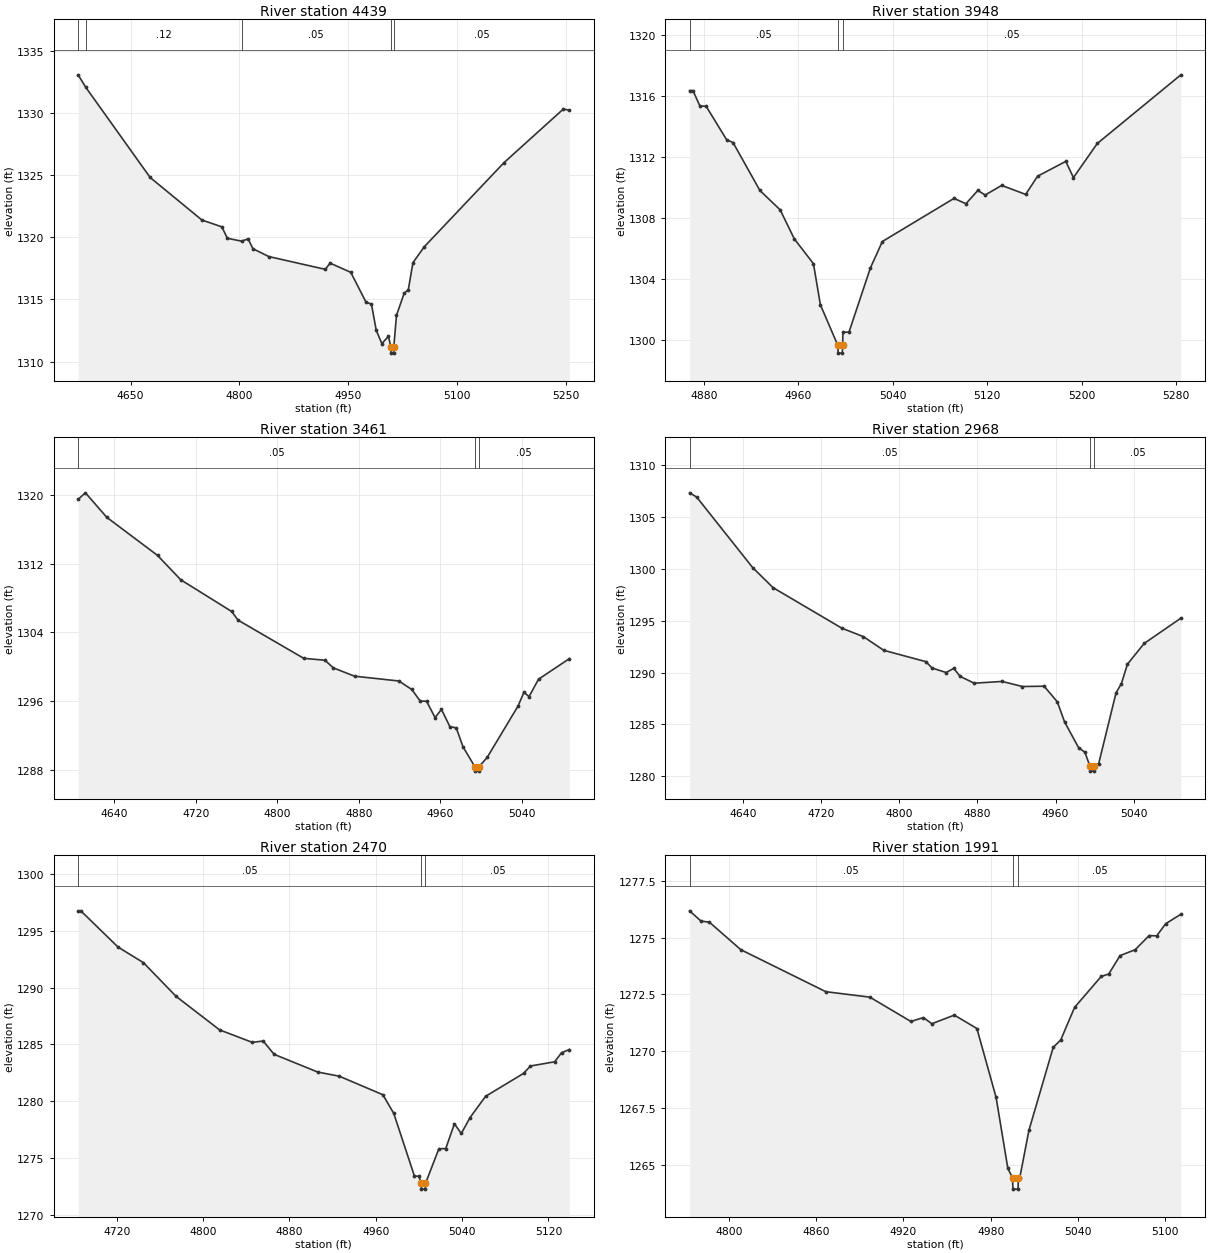
Type RM Length L Ch R = 1 ,4439    ,491,491,491
BEGIN DESCRIPTION:
LITTLE LLANO 036 9.0
END DESCRIPTION:
XS GIS Cut Line= 3
      2817655.69     10281503.11      2817380.25       10281183.
      2817155.66     10281303.13
#Sta/Elev= 30
  4577.7 1333.07  4588.1 1332.08    4677 1324.81  4748.3 1321.39  4775.8 1320.84
  4783.4 1319.92  4802.9 1319.69    4812 1319.87  4818.6 1319.08  4840.5 1318.45
  4918.4 1317.42    4925 1317.92  4953.5 1317.18  4974.4 1314.79    4982 1314.62
  4988.6 1312.51  4996.3 1311.45  5005.4 1312.03  5008.8 1311.18  5009.1 1310.68
  5012.6 1310.68  5012.8 1311.18  5016.5 1313.72  5027.1  1315.5  5032.8 1315.79
  5039.2 1317.96  5054.7 1319.23  5164.4 1325.99  5246.5 1330.32  5254.7 1330.22
#Mann= 5 ,-1 , 0
  4577.7     .05       0  4588.1     .12       0  4802.9     .05       0
  5008.8     .05       0  5012.8     .05       0
Bank Sta=5008.8,5012.8
XS Rating Curve= 0 ,0
Exp/Cntr=0.3,0.1

Type RM Length L Ch R = 1 ,3948    ,487,487,487
BEGIN DESCRIPTION:
LITTLE LLANO 036 8.0
END DESCRIPTION:
XS GIS Cut Line= 3
      2817555.72      10280703.1       2817436.5       10280760.
      2817155.69     10280803.11
#Sta/Elev= 30
  4867.9 1316.34  4870.7 1316.34  4876.5 1315.35    4882  1315.3  4899.2 1313.13
  4904.7 1312.94  4927.4 1309.81  4944.6 1308.54  4956.6 1306.64  4972.8 1305.02
  4978.7 1302.33  4993.5 1299.67  4993.7 1299.17  4997.2 1299.17  4997.5 1299.67
  4997.8 1300.54  5002.9 1300.54  5021.1 1304.75  5031.2 1306.47  5091.9 1309.29
    5102 1308.94  5112.1 1309.81  5118.3 1309.51  5132.3 1310.14  5152.6 1309.55
  5162.7 1310.74  5186.6 1311.71  5193.1 1310.65  5213.3 1312.88  5284.1 1317.37
#Mann= 3 ,-1 , 0
  4867.9     .05       0  4993.5     .05       0  4997.5     .05       0
Bank Sta=4993.5,4997.5
XS Rating Curve= 0 ,0
Exp/Cntr=0.3,0.1

Type RM Length L Ch R = 1 ,3461    ,493,493,493
BEGIN DESCRIPTION:
LITTLE LLANO 036 7.0
END DESCRIPTION:
XS GIS Cut Line= 3
      2817655.66     10280553.09       2817341.5       10280313.
      2817255.67     10280303.11
#Sta/Elev= 30
  4604.6 1319.48  4611.8 1320.24  4632.7 1317.39  4682.5 1312.95  4705.3 1310.11
  4755.2 1306.42  4761.5 1305.41  4825.9 1300.96  4846.7 1300.74  4854.9 1299.85
  4875.7 1298.88  4919.2 1298.32  4931.9 1297.33  4940.1 1295.99  4946.4 1295.96
  4954.7 1294.06    4961 1295.01  4969.2 1293.01  4975.5 1292.86  4982.1 1290.66
  4993.8 1288.32    4994 1287.82  4997.5 1287.82  4997.8 1288.32  5005.9 1289.43
  5036.1  1295.4  5041.9    1297  5046.9  1296.5  5056.2 1298.53  5086.4 1300.92
#Mann= 3 ,-1 , 0
  4604.6     .05       0  4993.8     .05       0  4997.8     .05       0
Bank Sta=4993.8,4997.8
XS Rating Curve= 0 ,0
Exp/Cntr=0.3,0.1

Type RM Length L Ch R = 1 ,2968    ,498,498,498
BEGIN DESCRIPTION:
LITTLE LLANO 036 6.0
END DESCRIPTION:
XS GIS Cut Line= 3
       2817855.7     10280153.12      2817536.25       10279889.
      2817455.68     10279853.11
#Sta/Elev= 30
  4585.5 1307.34  4592.7 1306.93    4650 1300.13  4670.8  1298.2  4741.2 1294.29
  4763.3 1293.47  4784.2 1292.15  4827.2 1291.06  4833.7 1290.44    4848 1290.01
  4855.8 1290.41  4862.3 1289.64  4876.7 1288.98  4905.3 1289.15  4926.1 1288.66
  4948.3 1288.69  4961.8 1287.18  4969.2 1285.25  4983.5 1282.77    4990 1282.32
  4995.1    1281  4995.4  1280.5  4998.9  1280.5  4999.1    1281  5004.1 1281.22
  5021.9 1288.06  5027.4 1288.95  5033.5 1290.81  5050.6 1292.81  5088.2 1295.25
#Mann= 3 ,-1 , 0
  4585.5     .05       0  4995.1     .05       0  4999.1     .05       0
Bank Sta=4995.1,4999.1
XS Rating Curve= 0 ,0
Exp/Cntr=0.3,0.1

Type RM Length L Ch R = 1 ,2470    ,479,479,479
BEGIN DESCRIPTION:
LITTLE LLANO 036 5.0
END DESCRIPTION:
XS GIS Cut Line= 3
      2817955.69     10279903.14      2817914.75       10279590.
      2817805.72     10279503.14
#Sta/Elev= 30
  4684.2 1296.75  4686.7 1296.75  4721.2 1293.56  4744.7 1292.19    4775 1289.22
  4815.3 1286.27  4845.6 1285.17  4855.7 1285.29  4865.8 1284.12  4906.1 1282.56
  4926.3 1282.19  4966.6 1280.56  4976.7 1278.92  4995.9 1273.39    5000 1273.39
  5002.1 1272.75  5002.4 1272.25  5005.9 1272.25  5006.1 1272.75  5018.5  1275.8
  5024.9 1275.82  5032.9    1278  5039.3 1277.15  5047.4 1278.55  5061.8 1280.42
    5097 1282.44  5103.4 1283.09  5125.8 1283.46  5132.2 1284.26  5139.4 1284.54
#Mann= 3 ,-1 , 0
  4684.2     .05       0  5002.1     .05       0  5006.1     .05       0
Bank Sta=5002.1,5006.1
XS Rating Curve= 0 ,0
Exp/Cntr=0.3,0.1

Type RM Length L Ch R = 1 ,1991    ,489,489,489
BEGIN DESCRIPTION:
LITTLE LLANO 036 4.0
END DESCRIPTION:
XS GIS Cut Line= 3
      2818455.71     10279403.13      2818261.75       10279285.
      2818155.64      10279253.1
#Sta/Elev= 30
  4772.9 1276.18  4780.7 1275.73  4786.5 1275.68  4808.1 1274.47  4866.6 1272.62
  4896.9 1272.38  4925.1 1271.31  4933.7 1271.48  4939.5 1271.21    4955 1271.59
  4970.5    1271  4983.7 1267.97  4991.8 1264.84    4995 1264.43  4995.3 1263.93
  4998.8 1263.93    4999 1264.43    5000 1264.43  5006.3 1266.52    5023 1270.17
  5028.2  1270.5  5037.7 1271.93    5056 1273.29  5061.2  1273.4    5069 1274.21
  5079.4 1274.47    5089 1275.09  5094.2 1275.08  5100.3 1275.61  5110.8 1276.03
#Mann= 3 ,-1 , 0
  4772.9     .05       0    4995     .03       0    4999     .05       0
Bank Sta=4995,4999
XS Rating Curve= 0 ,0
Exp/Cntr=0.3,0.1

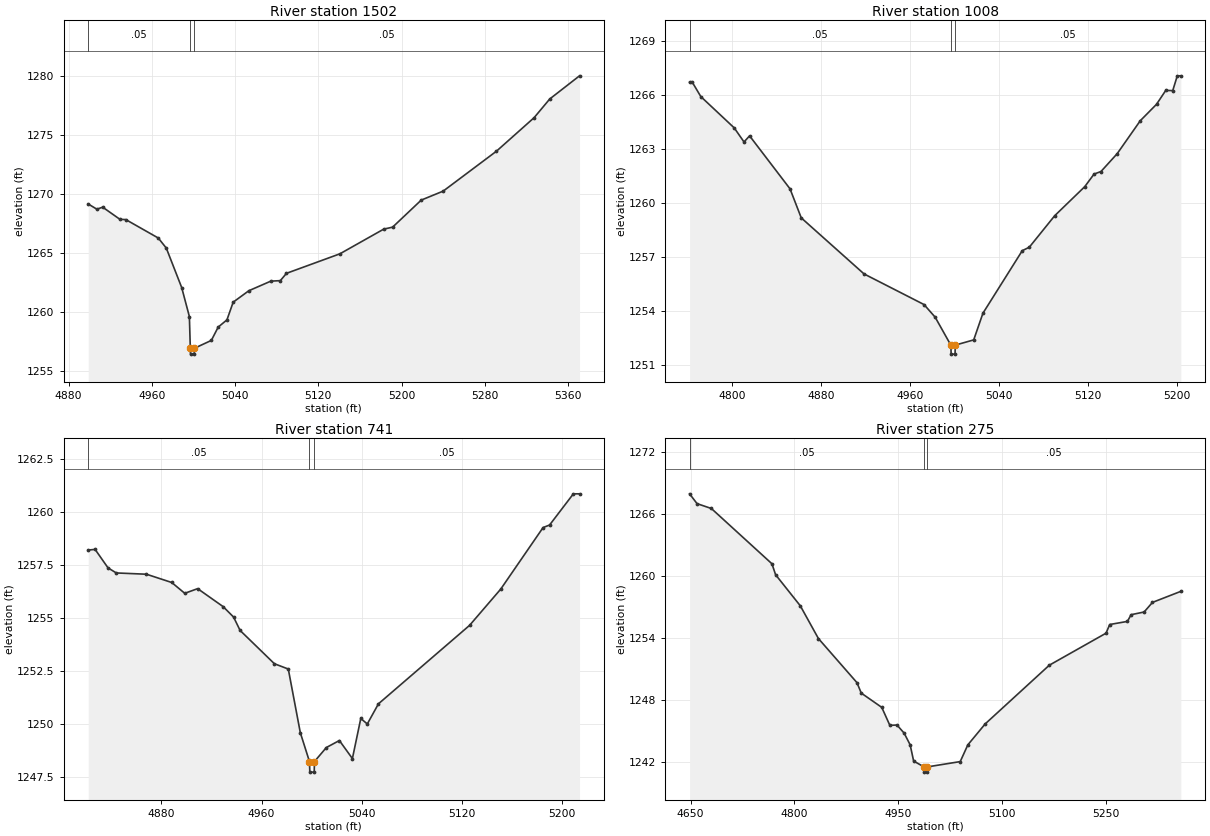
Type RM Length L Ch R = 1 ,1502    ,494,494,494
BEGIN DESCRIPTION:
LITTLE LLANO 036 3.0
END DESCRIPTION:
XS GIS Cut Line= 3
      2818505.66     10278953.07      2818459.75       10278863.
      2818255.71     10278553.15
#Sta/Elev= 30
  4898.9 1269.14  4907.2  1268.7  4912.8 1268.87  4929.4 1267.84    4935 1267.82
  4966.2 1266.26  4973.9 1265.41  4988.7 1262.07  4996.1 1259.61    4997 1256.93
  4997.2 1256.43  5000.7 1256.43    5001 1256.93  5017.2 1257.59  5023.8 1258.72
  5032.2 1259.33  5038.2 1260.83  5053.3  1261.8  5074.4 1262.61  5083.5 1262.65
  5089.4 1263.27  5140.7 1264.92  5182.8 1267.01  5191.4 1267.18  5218.9 1269.47
    5240 1270.23  5291.2 1273.61  5327.4 1276.45  5342.4 1278.03    5371 1279.99
#Mann= 3 ,-1 , 0
  4898.9     .05       0    4997     .03       0    5001     .05       0
Bank Sta=4997,5001
XS Rating Curve= 0 ,0
Exp/Cntr=0.3,0.1

Type RM Length L Ch R = 1 ,1008    ,267,267,267
BEGIN DESCRIPTION:
LITTLE LLANO 036 2.0
END DESCRIPTION:
XS GIS Cut Line= 3
      2818855.68     10278903.13      2818878.25       10278666.
      2818755.65     10278503.07
#Sta/Elev= 30
  4761.8 1266.71  4764.3 1266.71  4771.9 1265.92    4802 1264.18  4810.8  1263.4
  4815.8 1263.74  4852.2  1260.8  4862.3 1259.19  4918.8 1256.08  4972.8 1254.38
  4982.8 1253.68  4996.9 1252.13  4997.2 1251.63  5000.7 1251.63  5000.9 1252.13
  5017.5 1252.42  5025.8  1253.9  5061.2 1257.37  5067.5 1257.56  5090.4 1259.31
  5117.4 1260.92  5125.8 1261.62    5132 1261.76  5146.6 1262.75  5167.4 1264.58
    5182 1265.49  5190.3 1266.26  5196.6 1266.25  5200.7 1267.07  5203.9 1267.07
#Mann= 3 ,-1 , 0
  4761.8     .05       0  4996.9     .03       0  5000.9     .05       0
Bank Sta=4996.9,5000.9
XS Rating Curve= 0 ,0
Exp/Cntr=0.3,0.1

Type RM Length L Ch R = 1 ,741     ,466,466,466
BEGIN DESCRIPTION:
Mapping XS d2a4e3ab
END DESCRIPTION:
XS GIS Cut Line= 3
      2819115.67     10278848.53      2819148.23     10278696.59
      2819083.12      10278468.7
#Sta/Elev= 30
  4821.6 1258.22  4827.1 1258.25  4837.4 1257.38    4844 1257.14  4868.1 1257.08
  4888.3 1256.69  4898.7 1256.18    4909  1256.4  4929.4 1255.55  4937.7 1255.06
  4942.9 1254.43  4970.3 1252.86  4981.4 1252.61    4991 1249.61  4998.3 1248.25
  4998.6 1247.75  5002.1 1247.75  5002.3 1248.25  5011.8 1248.91  5022.2 1249.24
  5032.6 1248.39  5039.3 1250.28  5044.5 1250.02  5053.4 1250.97  5126.2 1254.67
  5151.1 1256.38  5184.9 1259.28  5190.1  1259.4  5209.1 1260.87    5214 1260.87
#Mann= 3 ,-1 , 0
  4821.6     .05       0  4998.3     .03       0  5002.3     .05       0
Bank Sta=4998.3,5002.3
XS Rating Curve= 0 ,0
Exp/Cntr=0.3,0.1

Type RM Length L Ch R = 1 ,275     ,0,0,0
BEGIN DESCRIPTION:
LITTLE LLANO 036 1.0
END DESCRIPTION:
XS GIS Cut Line= 3
      2819679.92     10278913.61       2819593.5       10278573.
      2819255.65      10278453.1
#Sta/Elev= 30
  4648.6 1267.94  4659.4 1266.99  4680.1 1266.52  4767.6 1261.17  4772.9 1260.11
  4808.6  1257.1  4834.8 1253.93  4890.5 1249.66  4896.7 1248.65  4926.3 1247.27
    4938 1245.53  4948.3 1245.56  4958.6 1244.78  4967.3 1243.65  4972.4 1242.07
  4987.6  1241.5  4987.8    1241  4991.3    1241  4991.6  1241.5  5039.7 1242.02
  5050.7 1243.64  5075.8 1245.67  5168.4 1251.35  5250.4 1254.45  5255.7 1255.29
  5281.3 1255.59  5286.6 1256.24  5305.4  1256.5  5317.5 1257.43  5358.5  1258.5
#Mann= 3 ,-1 , 0
  4648.6     .05       0  4987.6     .05       0  4991.6     .05       0
Bank Sta=4987.6,4991.6
XS Rating Curve= 0 ,0
Exp/Cntr=0.3,0.1

Chan Stop Cuts=-1
Use User Specified Reach Order=0
Composite Channel Slope=5