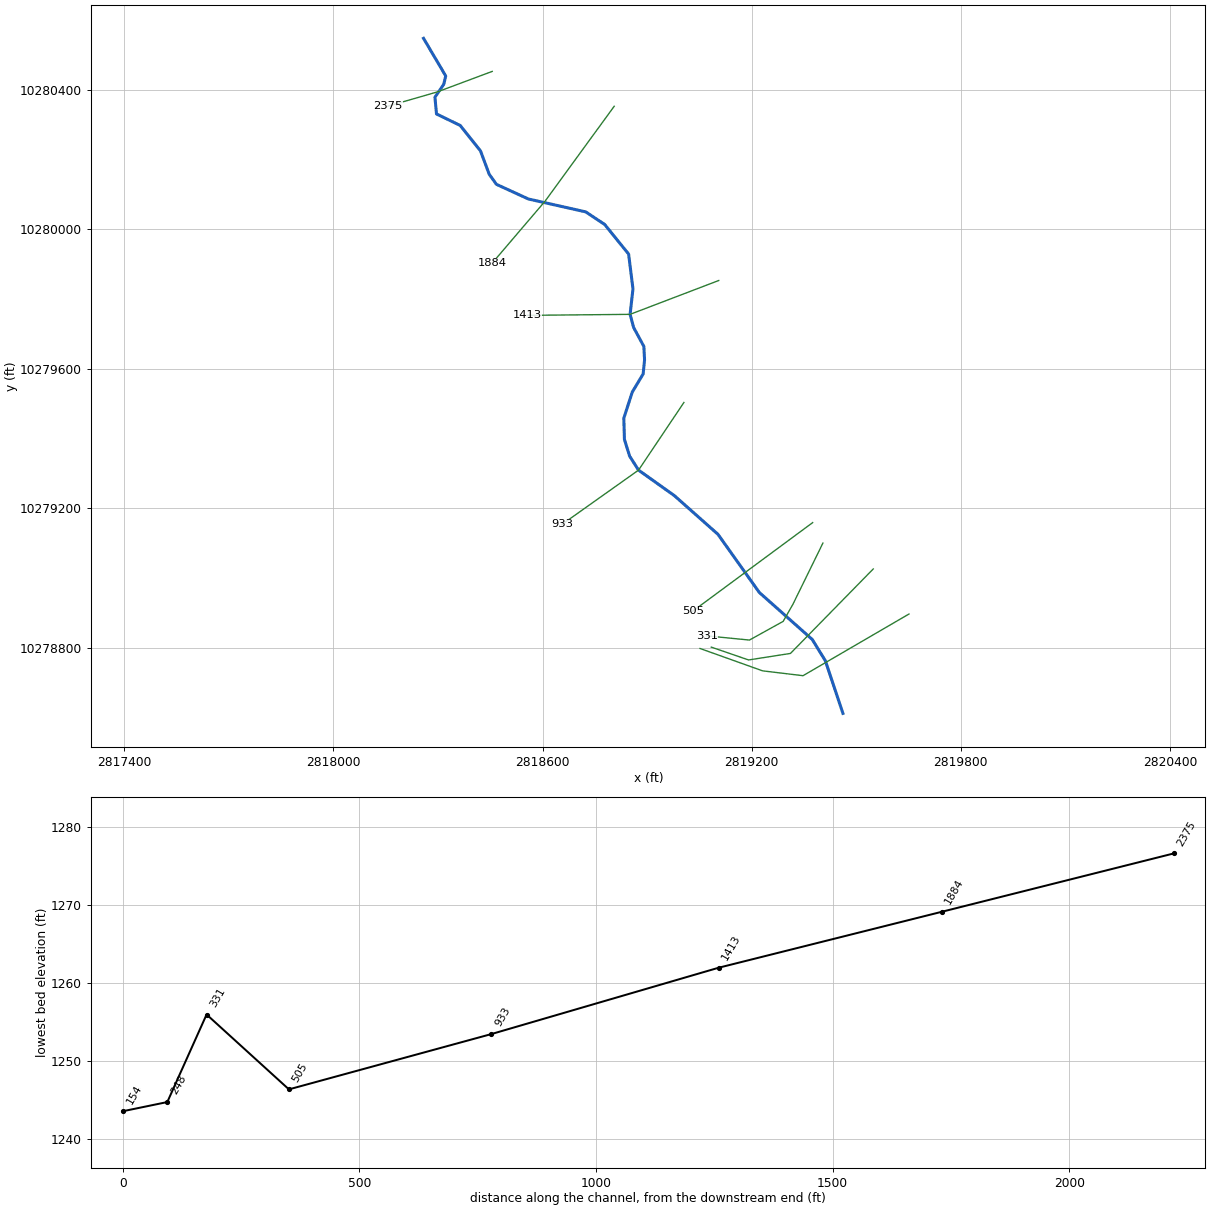
--- LITTLE LLANO 037.prj (project) ---

Proj Title=LITTLE LLANO 037 Base Level Engineering
Current Plan=p01
Default Exp/Contr=0.3,0.1
English Units
Geom File=g01
Flow File=f01
Plan File=p01
BEGIN DESCRIPTION:
LITTLE LLANO 037
END DESCRIPTION:

--- LITTLE LLANO 037.p01 (plan) ---

Plan Title=Multiple Run
Short Identifier=Multiple
Geom File=g01
Flow File=f01
Subcritical Flow
K Sum by GR= 0
Std Step Tol= 0.01
Critical Tol= 0.01
Num of Std Step Trials= 20
Max Error Tol= 0.3
Flow Tol Ratio= 0.001
Split Flow NTrial= 30
Split Flow Tol= 0.02
Split Flow Ratio= 0.02
Log Output Level= 0
Friction Slope Method= 1
Unsteady Friction Slope Method= 2
Unsteady Bridges Friction Slope Method= 1
Parabolic Critical Depth
Global Vel Dist=  1 , 1 , 1
Global Log Level= 0
CheckData=True
Encroach Param= -1, 0, 0, 0
BEGIN DESCRIPTION:
Multiple Run
END DESCRIPTION:

--- LITTLE LLANO 037.f01 (steady flow) ---

Flow Title=Multiple
Number of Profiles=7
Profile Names=10-year,25-year,50-year,1pct_min,100-year,1pct_plu,500-year
River Rch & RM= LITTLE LLANO 037,Reach-1,2375
     180     276     411     329     544     898     774
Boundary for River Rch & Prof#=LITTLE LLANO 037,Reach-1,1
Up Type=0
Dn Type=3
Dn Slope=0.005
Boundary for River Rch & Prof#=LITTLE LLANO 037,Reach-1,2
Up Type=0
Dn Type=3
Dn Slope=0.005
Boundary for River Rch & Prof#=LITTLE LLANO 037,Reach-1,3
Up Type=0
Dn Type=3
Dn Slope=0.005
Boundary for River Rch & Prof#=LITTLE LLANO 037,Reach-1,4
Up Type=0
Dn Type=3
Dn Slope=0.005
Boundary for River Rch & Prof#=LITTLE LLANO 037,Reach-1,5
Up Type=0
Dn Type=3
Dn Slope=0.005
Boundary for River Rch & Prof#=LITTLE LLANO 037,Reach-1,6
Up Type=0
Dn Type=3
Dn Slope=0.005
Boundary for River Rch & Prof#=LITTLE LLANO 037,Reach-1,7
Up Type=0
Dn Type=3
Dn Slope=0.005

--- LITTLE LLANO 037.g01 (geometry) ---

Geom Title=Existing Conditions

River Reach=LITTLE LLANO 037,Reach-1
Reach XY= 30
      2818258.50     10280548.00      2818322.25     10280440.00
      2818316.50     10280416.00      2818291.25     10280379.00
      2818295.75     10280331.00      2818363.75     10280298.00
      2818422.00     10280225.00      2818447.00     10280158.00
      2818467.75     10280129.00      2818559.50     10280087.00
      2818724.00     10280050.00      2818778.25     10280014.00
      2818847.00     10279929.00      2818859.50     10279829.00
      2818851.25     10279756.00      2818861.50     10279718.00
      2818890.75     10279664.00      2818892.75     10279625.00
      2818888.75     10279585.00      2818857.50     10279533.00
      2818833.25     10279458.00      2818835.00     10279397.00
      2818850.00     10279349.00      2818875.50     10279309.00
      2818978.00     10279236.00      2819103.25     10279125.00
      2819222.00     10278958.00      2819374.00     10278823.00
      2819411.50     10278762.00      2819462.00     10278611.00

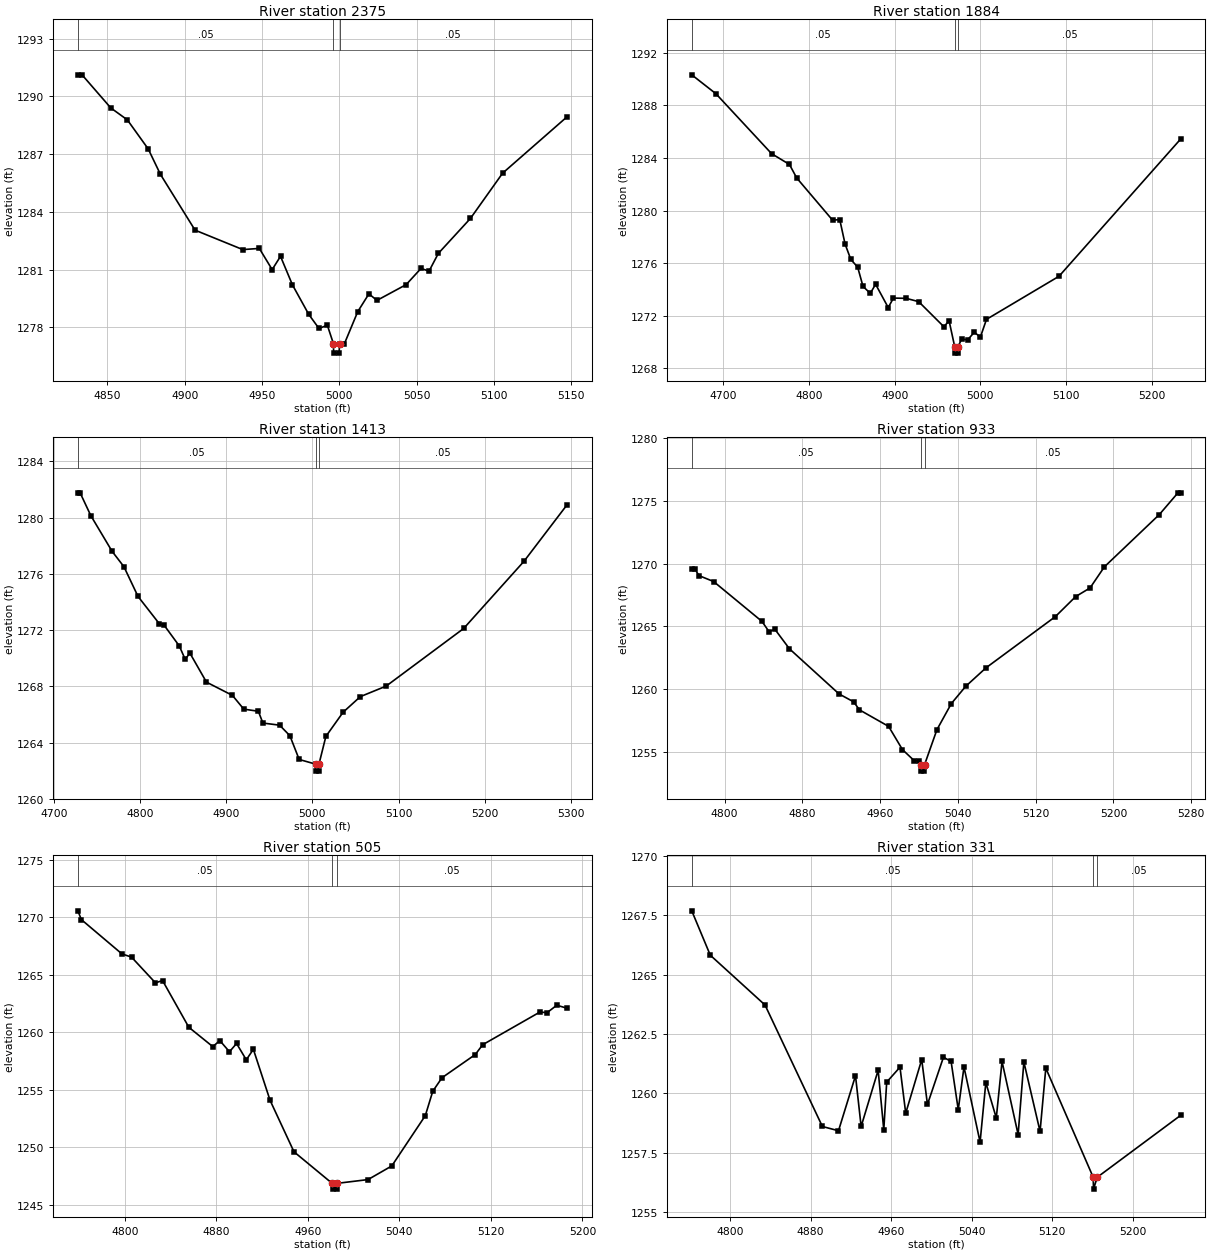
Type RM Length L Ch R = 1,2375,491,491,491
BEGIN DESCRIPTION:
LITTLE LLANO 037 5.0
END DESCRIPTION:
XS GIS Cut Line= 3
      2818455.68     10280453.11      2818297.25     10280394.00
      2818155.64     10280353.10
#Sta/Elev= 30
  4830.9 1291.12  4833.6 1291.12  4852.2 1289.40  4862.9 1288.78  4876.4 1287.27
  4884.3 1285.95  4906.7 1283.05  4937.6 1282.04  4948.3 1282.10  4956.6 1281.00
  4962.0 1281.69  4969.7 1280.21  4980.3 1278.67  4986.9 1277.94  4992.3 1278.11
  4996.2 1277.16  4996.4 1276.66  4999.9 1276.66  5000.2 1277.16  5003.4 1277.16
  5012.0 1278.82  5019.2 1279.74  5024.4 1279.40  5043.3 1280.22  5052.9 1281.06
  5058.1 1280.92  5064.1 1281.84  5084.9 1283.66  5105.7 1286.01  5147.4 1288.94
#Mann=3,-1,0
  4830.9    0.05       0  4996.2    0.03       0  5000.2    0.05       0
Bank Sta=4996.2,5000.2
Exp/Cntr=0.3,0.1

Type RM Length L Ch R = 1,1884,471,471,471
BEGIN DESCRIPTION:
LITTLE LLANO 037 4.0
END DESCRIPTION:
XS GIS Cut Line= 3
      2818805.66     10280353.09      2818607.50     10280081.00
      2818455.66     10279903.08
#Sta/Elev= 30
  4663.4 1290.33  4691.6 1288.89  4756.5 1284.33  4777.3 1283.51  4785.8 1282.48
  4827.6 1279.27  4836.0 1279.31  4842.2 1277.45  4848.9 1276.28  4856.9 1275.69
  4863.1 1274.23  4871.6 1273.70  4877.8 1274.39  4892.5 1272.62  4898.6 1273.34
  4913.3 1273.32  4928.0 1273.07  4957.4 1271.16  4963.5 1271.61  4970.0 1269.65
  4970.3 1269.15  4973.8 1269.15  4974.0 1269.65  4978.2 1270.23  4985.0 1270.15
  4992.9 1270.74  5000.0 1270.37  5007.1 1271.72  5091.7 1275.00  5233.9 1285.47
#Mann=3,-1,0
  4663.4    0.05       0  4970.0    0.03       0  4974.0    0.05       0
Bank Sta=4970,4974
Exp/Cntr=0.3,0.1

Type RM Length L Ch R = 1,1413,480,480,480
BEGIN DESCRIPTION:
LITTLE LLANO 037 3.0
END DESCRIPTION:
XS GIS Cut Line= 3
      2819105.65     10279853.10      2818851.25     10279756.00
      2818555.66     10279753.11
#Sta/Elev= 30
  4727.7 1281.77  4730.3 1281.77  4742.7 1280.15  4767.4 1277.61  4781.2 1276.51
  4797.5 1274.40  4822.2 1272.46  4827.6 1272.37  4845.4 1270.88  4852.3 1269.92
  4857.7 1270.37  4877.0 1268.30  4907.1 1267.36  4920.3 1266.38  4937.2 1266.23
  4942.5 1265.39  4961.9 1265.24  4973.8 1264.49  4984.6 1262.80  5003.6 1262.47
  5003.8 1261.97  5007.3 1261.97  5007.6 1262.47  5015.6 1264.44  5035.6 1266.16
  5055.6 1267.27  5085.6 1268.02  5175.6 1272.12  5245.6 1276.90  5295.6 1280.92
#Mann=3,-1,0
  4727.7    0.05       0  5003.6    0.03       0  5007.6    0.05       0
Bank Sta=5003.6,5007.6
Exp/Cntr=0.3,0.1

Type RM Length L Ch R = 1,933,428,428,428
BEGIN DESCRIPTION:
LITTLE LLANO 037 2.0
END DESCRIPTION:
XS GIS Cut Line= 3
      2819005.67     10279503.09      2818875.50     10279309.00
      2818655.67     10279153.10
#Sta/Elev= 30
  4766.3 1269.59  4769.3 1269.59  4773.8 1269.05  4788.8 1268.58  4838.5 1265.40
  4845.8 1264.58  4851.8 1264.77  4866.8 1263.21  4917.8 1259.61  4932.8 1258.98
  4938.8 1258.34  4968.8 1257.02  4983.0 1255.17  4995.3 1254.27  5000.0 1254.27
  5001.7 1253.95  5002.0 1253.45  5005.5 1253.45  5005.7 1253.95  5018.5 1256.76
  5033.3 1258.84  5048.0 1260.21  5068.9 1261.69  5140.3 1265.78  5161.2 1267.38
  5176.0 1268.07  5190.7 1269.75  5247.3 1273.93  5266.4 1275.66  5269.5 1275.66
#Mann=3,-1,0
  4766.3    0.05       0  5001.7    0.03       0  5005.7    0.05       0
Bank Sta=5001.7,5005.7
Exp/Cntr=0.3,0.1

Type RM Length L Ch R = 1,505,174,174,174
BEGIN DESCRIPTION:
Mapping XS e530b413
END DESCRIPTION:
XS GIS Cut Line= 2
      2819375.15     10279158.42      2819031.21     10278904.36
#Sta/Elev= 30
  4759.0 1270.57  4762.0 1269.81  4797.5 1266.82  4805.9 1266.54  4826.8 1264.30
  4833.0 1264.50  4856.0 1260.43  4876.9 1258.75  4883.1 1259.27  4891.5 1258.30
  4897.7 1259.02  4906.2 1257.60  4912.4 1258.51  4927.0 1254.07  4947.9 1249.59
  4981.3 1246.84  4981.6 1246.34  4985.1 1246.34  4985.3 1246.84  5012.6 1247.17
  5033.4 1248.36  5062.7 1252.74  5069.2 1254.86  5077.3 1256.04  5106.4 1258.06
  5112.8 1258.91  5162.9 1261.76  5169.1 1261.70  5177.6 1262.35  5186.6 1262.09
#Mann=3,-1,0
  4759.0    0.05       0  4981.3    0.05       0  4985.3    0.05       0
Bank Sta=4981.3,4985.3
Exp/Cntr=0.3,0.1

Type RM Length L Ch R = 1,331,83,83,83
BEGIN DESCRIPTION:
Mapping XS 05118687
END DESCRIPTION:
XS GIS Cut Line= 5
      2819404.56     10279099.67      2819318.13     10278923.36
      2819290.48     10278874.96      2819193.68     10278821.38
      2819070.91     10278833.48
#Sta/Elev= 30
  4762.0 1267.69  4780.4 1265.82  4834.8 1263.72  4891.8 1258.60  4907.8 1258.42
  4924.7 1260.74  4930.3 1258.60  4947.2 1260.97  4952.8 1258.46  4955.7 1260.47
  4968.9 1261.10  4974.6 1259.16  4990.5 1261.42  4996.2 1259.53  5012.1 1261.52
  5019.7 1261.34  5026.8 1259.31  5032.5 1261.11  5048.5 1257.94  5054.2 1260.45
  5064.6 1258.96  5070.3 1261.34  5086.3 1258.26  5092.0 1261.32  5108.1 1258.39
  5113.8 1261.06  5160.9 1256.46  5161.2 1255.96  5164.9 1256.46  5248.1 1259.08
#Mann=3,-1,0
  4762.0    0.05       0  5160.9    0.05       0  5164.9    0.05       0
Bank Sta=5160.9,5164.9
Exp/Cntr=0.3,0.1

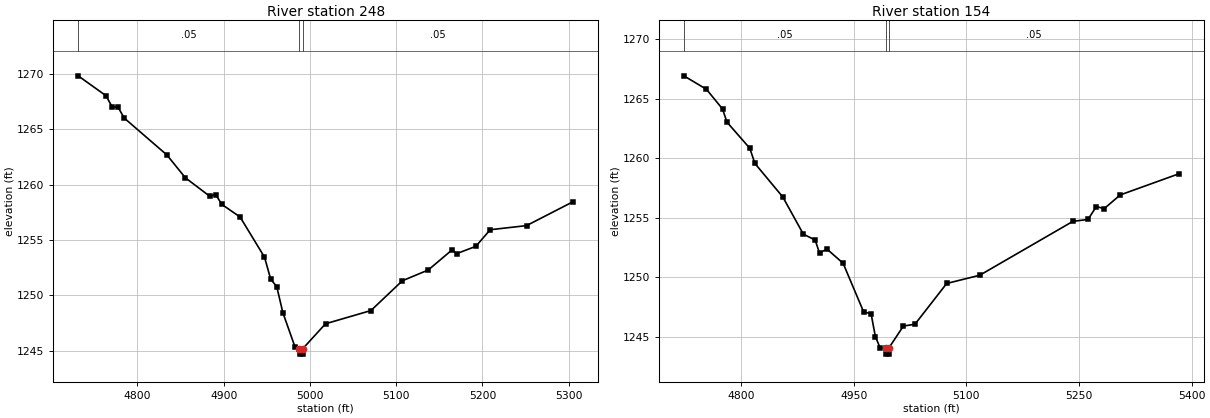
Type RM Length L Ch R = 1,248,94,94,94
BEGIN DESCRIPTION:
Mapping XS 8bf975cc
END DESCRIPTION:
XS GIS Cut Line= 4
      2819548.95     10279025.41      2819311.42     10278783.02
      2819191.28     10278764.27      2819084.30     10278801.09
#Sta/Elev= 30
  4731.3 1269.81  4763.5 1268.02  4770.6 1267.02  4777.6 1266.97  4784.7 1266.00
  4834.2 1262.67  4855.5 1260.62  4883.8 1258.95  4890.8 1259.09  4897.9 1258.21
  4919.0 1257.08  4947.3 1253.46  4954.5 1251.47  4961.5 1250.80  4968.6 1248.45
  4982.8 1245.33  4987.8 1245.21  4988.0 1244.71  4991.5 1244.71  4991.8 1245.21
  5018.1 1247.45  5070.7 1248.64  5107.2 1251.33  5137.2 1252.30  5164.9 1254.12
  5170.0 1253.77  5192.3 1254.43  5209.0 1255.93  5251.1 1256.30  5305.4 1258.47
#Mann=3,-1,0
  4731.3    0.05       0  4987.8    0.05       0  4991.8    0.05       0
Bank Sta=4987.8,4991.8
Exp/Cntr=0.3,0.1

Type RM Length L Ch R = 1,154,0,0,0
BEGIN DESCRIPTION:
LITTLE LLANO 037 1.0
END DESCRIPTION:
XS GIS Cut Line= 4
      2819651.67     10278896.20      2819347.53     10278719.14
      2819231.56     10278733.02      2819051.91     10278797.20
#Sta/Elev= 30
  4723.7 1266.92  4753.8 1265.79  4775.3 1264.13  4781.1 1263.03  4811.6 1260.83
  4818.3 1259.56  4855.6 1256.73  4882.9 1253.61  4898.6 1253.12  4904.4 1252.03
  4914.3 1252.36  4935.8 1251.17  4963.1 1247.09  4973.1 1246.92  4978.8 1245.01
  4985.2 1244.04  4992.6 1244.03  4992.8 1243.53  4996.3 1243.53  4996.6 1244.03
  5016.1 1245.89  5031.5 1246.04  5073.8 1249.47  5117.8 1250.16  5241.9 1254.69
  5262.0 1254.85  5273.0 1255.93  5283.6 1255.76  5304.9 1256.91  5383.2 1258.69
#Mann=3,-1,0
  4723.7    0.05       0  4992.6    0.03       0  4996.6    0.05       0
Bank Sta=4992.6,4996.6
Exp/Cntr=0.3,0.1

Chan Stop Cuts=-1