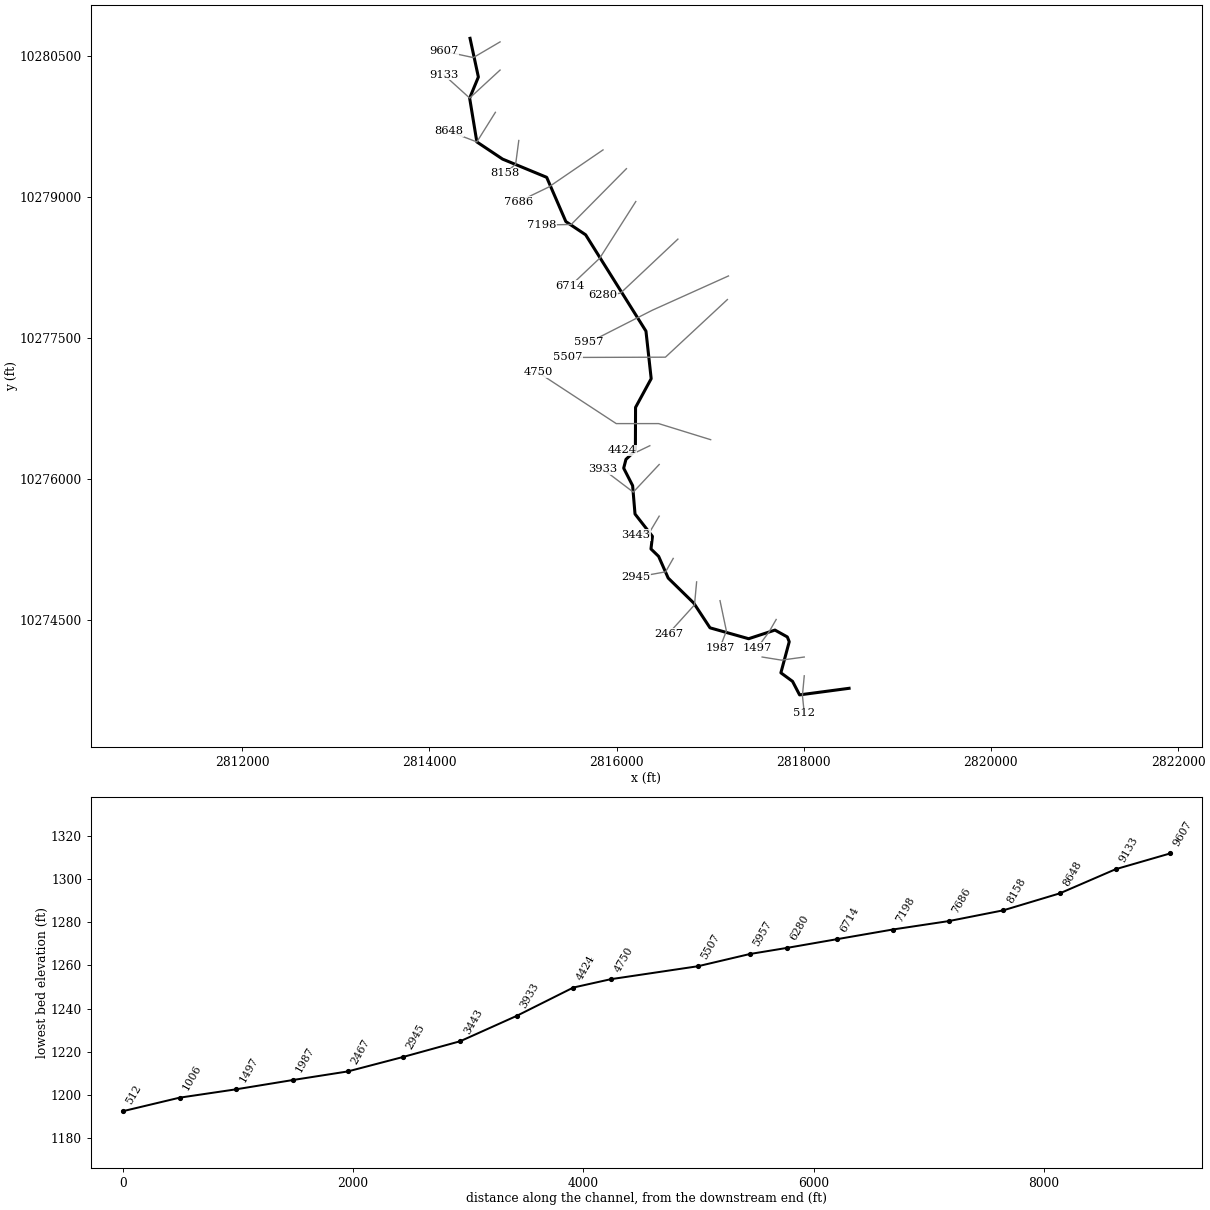
--- LITTLE LLANO 038.prj (project) ---

Proj Title=LITTLE LLANO 038 Base Level Engineering
Current Plan=p01
Default Exp/Contr=0.3,0.1
English Units
Geom File=g01
Flow File=f01
Plan File=p01
BEGIN DESCRIPTION:
LITTLE LLANO 038
END DESCRIPTION:

--- LITTLE LLANO 038.p01 (plan) ---

Plan Title=Multiple Run
Short Identifier=Multiple
Geom File=g01
Flow File=f01
Subcritical Flow
K Sum by GR= 0
Std Step Tol= 0.01
Critical Tol= 0.01
Num of Std Step Trials= 20
Max Error Tol= 0.3
Flow Tol Ratio= 0.001
Split Flow NTrial= 30
Split Flow Tol= 0.02
Split Flow Ratio= 0.02
Log Output Level= 0
Friction Slope Method= 1
Unsteady Friction Slope Method= 2
Unsteady Bridges Friction Slope Method= 1
Parabolic Critical Depth
Global Vel Dist=  1 , 1 , 1
Global Log Level= 0
CheckData=True
Encroach Param= -1, 0, 0, 0
BEGIN DESCRIPTION:
Multiple Run
END DESCRIPTION:

--- LITTLE LLANO 038.f01 (steady flow) ---

Flow Title=Multiple
Number of Profiles=7
Profile Names=10-year,25-year,50-year,1pct_min,100-year,1pct_plu,500-year
River Rch & RM= LITTLE LLANO 038,Reach-1,9607
     436     705    1087     832    1473    2611    2062
River Rch & RM= LITTLE LLANO 038,Reach-1,1006
     476     776    1177     879    1599    2909    2238
Boundary for River Rch & Prof#=LITTLE LLANO 038,Reach-1,1
Up Type=0
Dn Type=3
Dn Slope=0.005
Boundary for River Rch & Prof#=LITTLE LLANO 038,Reach-1,2
Up Type=0
Dn Type=3
Dn Slope=0.005
Boundary for River Rch & Prof#=LITTLE LLANO 038,Reach-1,3
Up Type=0
Dn Type=3
Dn Slope=0.005
Boundary for River Rch & Prof#=LITTLE LLANO 038,Reach-1,4
Up Type=0
Dn Type=3
Dn Slope=0.005
Boundary for River Rch & Prof#=LITTLE LLANO 038,Reach-1,5
Up Type=0
Dn Type=3
Dn Slope=0.005
Boundary for River Rch & Prof#=LITTLE LLANO 038,Reach-1,6
Up Type=0
Dn Type=3
Dn Slope=0.005
Boundary for River Rch & Prof#=LITTLE LLANO 038,Reach-1,7
Up Type=0
Dn Type=3
Dn Slope=0.005

--- LITTLE LLANO 038.g01 (geometry) ---

Geom Title=Existing Conditions

River Reach=LITTLE LLANO 038,Reach-1
Reach XY= 30
      2814435.00     10280691.00      2814524.00     10280279.00
      2814430.75     10280055.00      2814507.75     10279588.00
      2814782.75     10279405.00      2815253.75     10279211.00
      2815458.50     10278740.00      2815670.00     10278599.00
      2816314.50     10277573.00      2816370.25     10277067.00
      2816203.25     10276761.00      2816201.50     10276302.00
      2816100.75     10276208.00      2816076.50     10276114.00
      2816172.00     10275928.00      2816197.50     10275626.00
      2816383.75     10275388.00      2816368.00     10275254.00
      2816449.75     10275175.00      2816552.00     10274944.00
      2816824.75     10274678.00      2816998.75     10274414.00
      2817411.50     10274298.00      2817692.75     10274390.00
      2817824.75     10274317.00      2817845.25     10274266.00
      2817756.00     10273935.00      2817880.50     10273844.00
      2817955.75     10273700.00      2818484.50     10273770.00

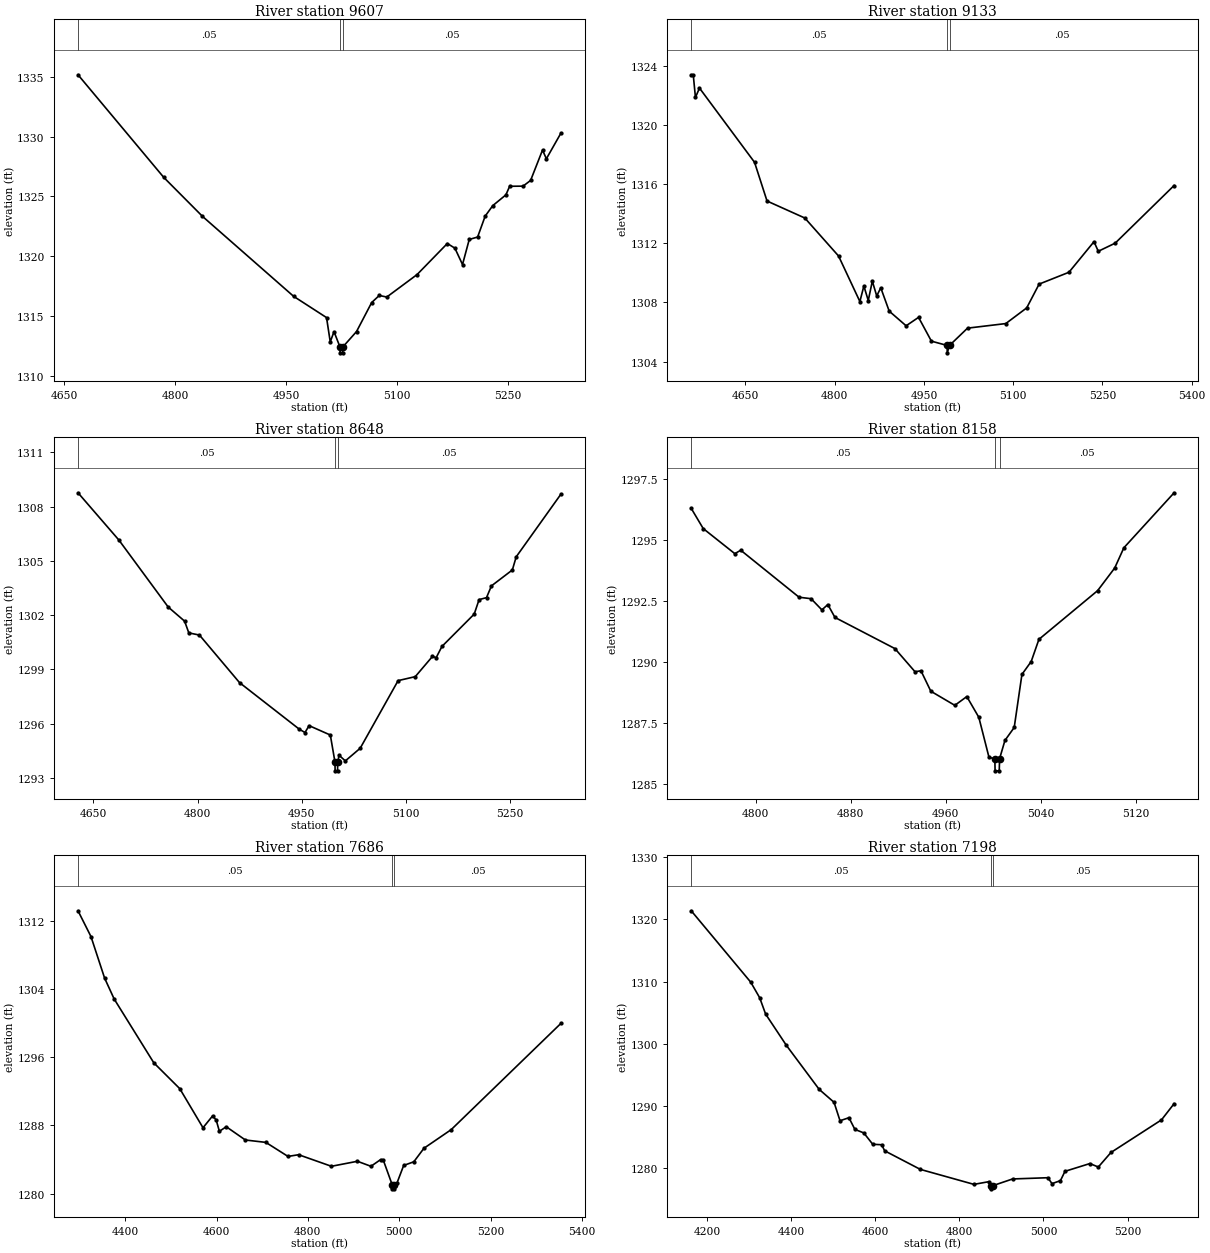
Type RM Length L Ch R = 1,9607,474,474,474
BEGIN DESCRIPTION:
LITTLE LLANO 038 20.0
END DESCRIPTION:
XS GIS Cut Line= 3
      2814755.71     10280653.13      2814470.00     10280486.00
      2814155.68     10280553.11
#Sta/Elev= 30
  4669.0 1335.18  4784.9 1326.59  4837.2 1323.33  4960.3 1316.64  5004.8 1314.86
  5009.8 1312.83  5014.9 1313.68  5022.9 1312.41  5023.1 1311.91  5026.6 1311.91
  5026.9 1312.41  5045.3 1313.69  5065.8 1316.12  5076.0 1316.71  5086.2 1316.58
  5127.1 1318.46  5168.0 1321.06  5178.2 1320.67  5188.5 1319.30  5197.6 1321.40
  5208.9 1321.60  5219.1 1323.35  5229.4 1324.23  5247.1 1325.13  5252.2 1325.85
  5270.3 1325.86  5280.5 1326.34  5296.6 1328.88  5301.8 1328.15  5321.4 1330.29
#Mann=3,-1,0
  4669.0    0.05       0  5022.9    0.05       0  5026.9    0.05       0
Bank Sta=5022.9,5026.9
Exp/Cntr=0.3,0.1

Type RM Length L Ch R = 1,9133,485,485,485
BEGIN DESCRIPTION:
LITTLE LLANO 038 19.0
END DESCRIPTION:
XS GIS Cut Line= 3
      2814755.71     10280353.13      2814430.75     10280055.00
      2814155.71     10280303.09
#Sta/Elev= 30
  4559.0 1323.40  4562.4 1323.40  4566.1 1321.87  4572.9 1322.50  4665.4 1317.48
  4686.4 1314.86  4749.9 1313.71  4806.6 1311.14  4842.4 1308.06  4849.1 1309.11
  4856.5 1308.13  4863.3 1309.44  4870.7 1308.44  4877.5 1308.99  4891.7 1307.41
  4920.1 1306.42  4941.0 1306.99  4962.6 1305.38  4989.0 1305.09  4989.2 1304.59
  4993.0 1305.09  5023.3 1306.26  5087.6 1306.57  5122.7 1307.63  5143.6 1309.24
  5193.7 1310.04  5235.8 1312.11  5243.0 1311.46  5271.4 1312.01  5370.4 1315.91
#Mann=3,-1,0
  4559.0    0.05       0  4989.0    0.05       0  4993.0    0.05       0
Bank Sta=4989,4993
Exp/Cntr=0.3,0.1

Type RM Length L Ch R = 1,8648,490,490,490
BEGIN DESCRIPTION:
LITTLE LLANO 038 18.0
END DESCRIPTION:
XS GIS Cut Line= 3
      2814705.67     10279903.09      2814507.75     10279588.00
      2814205.64     10279703.13
#Sta/Elev= 30
  4627.9 1308.77  4686.9 1306.15  4757.8 1302.45  4781.4 1301.67  4787.5 1301.02
  4802.8 1300.90  4860.5 1298.27  4946.7 1295.69  4954.8 1295.51  4960.7 1295.89
  4991.3 1295.37  4997.9 1293.89  4998.2 1293.39  5001.7 1293.39  5001.9 1293.89
  5003.9 1294.25  5012.9 1293.94  5034.3 1294.64  5088.9 1298.38  5113.6 1298.60
  5138.4 1299.72  5143.7 1299.65  5152.0 1300.27  5198.5 1302.06  5205.5 1302.86
  5216.2 1302.97  5223.3 1303.62  5253.4 1304.50  5259.0 1305.23  5323.3 1308.69
#Mann=3,-1,0
  4627.9    0.05       0  4997.9    0.05       0  5001.9    0.05       0
Bank Sta=4997.9,5001.9
Exp/Cntr=0.3,0.1

Type RM Length L Ch R = 1,8158,472,472,472
BEGIN DESCRIPTION:
LITTLE LLANO 038 17.0
END DESCRIPTION:
XS GIS Cut Line= 3
      2814955.68     10279603.09      2814922.25     10279351.00
      2814805.70     10279253.12
#Sta/Elev= 30
  4745.7 1296.31  4755.8 1295.48  4782.4 1294.45  4787.4 1294.59  4836.5 1292.66
  4846.6 1292.60  4855.7 1292.14  4860.7 1292.36  4866.7 1291.83  4917.2 1290.55
  4934.1 1289.60  4939.1 1289.64  4947.4 1288.80  4967.6 1288.22  4977.7 1288.58
  4987.8 1287.73  4996.4 1286.08  5001.3 1286.03  5001.5 1285.53  5005.0 1285.53
  5005.3 1286.03  5009.8 1286.78  5017.6 1287.31  5024.1 1289.49  5031.9 1290.02
  5038.4 1290.93  5087.8 1292.93  5102.2 1293.86  5109.9 1294.69  5152.2 1296.95
#Mann=3,-1,0
  4745.7    0.05       0  5001.3    0.05       0  5005.3    0.05       0
Bank Sta=5001.3,5005.3
Exp/Cntr=0.3,0.1

Type RM Length L Ch R = 1,7686,488,488,488
BEGIN DESCRIPTION:
LITTLE LLANO 038 16.0
END DESCRIPTION:
XS GIS Cut Line= 3
      2815855.66     10279503.09      2815274.50     10279107.00
      2814955.70     10278953.12
#Sta/Elev= 30
  4296.7 1313.23  4325.1 1310.20  4355.0 1305.31  4375.9 1302.86  4462.7 1295.36
  4519.6 1292.32  4570.4 1287.73  4591.4 1289.12  4599.2 1288.65  4606.3 1287.31
  4621.3 1287.85  4663.2 1286.29  4708.0 1286.01  4756.5 1284.36  4779.8 1284.56
  4851.6 1283.20  4908.5 1283.79  4938.1 1283.20  4959.4 1283.99  4965.4 1283.89
  4984.5 1281.05  4984.7 1280.55  4988.2 1280.55  4988.5 1281.05  4995.3 1281.26
  5009.8 1283.30  5032.0 1283.73  5054.2 1285.32  5113.9 1287.51  5354.0 1299.99
#Mann=3,-1,0
  4296.7    0.05       0  4984.5    0.03       0  4988.5    0.05       0
Bank Sta=4984.5,4988.5
Exp/Cntr=0.3,0.1

Type RM Length L Ch R = 1,7198,484,484,484
BEGIN DESCRIPTION:
LITTLE LLANO 038 15.0
END DESCRIPTION:
XS GIS Cut Line= 3
      2816105.70     10279303.13      2815516.00     10278709.00
      2815205.66     10278703.11
#Sta/Elev= 30
  4162.9 1321.39  4304.3 1309.90  4325.6 1307.39  4339.7 1304.76  4389.2 1299.71
  4467.0 1292.64  4502.3 1290.56  4516.5 1287.59  4537.7 1288.08  4551.8 1286.20
  4573.0 1285.63  4594.3 1283.80  4615.5 1283.73  4622.6 1282.75  4707.4 1279.76
  4834.7 1277.35  4870.0 1277.78  4875.1 1277.13  4875.4 1276.63  4879.1 1277.13
  4926.6 1278.22  5010.3 1278.42  5020.3 1277.47  5040.3 1277.95  5051.1 1279.45
  5110.3 1280.70  5130.3 1280.14  5160.3 1282.48  5280.4 1287.73  5310.4 1290.34
#Mann=3,-1,0
  4162.9    0.05       0  4875.1    0.05       0  4879.1    0.05       0
Bank Sta=4875.1,4879.1
Exp/Cntr=0.3,0.1

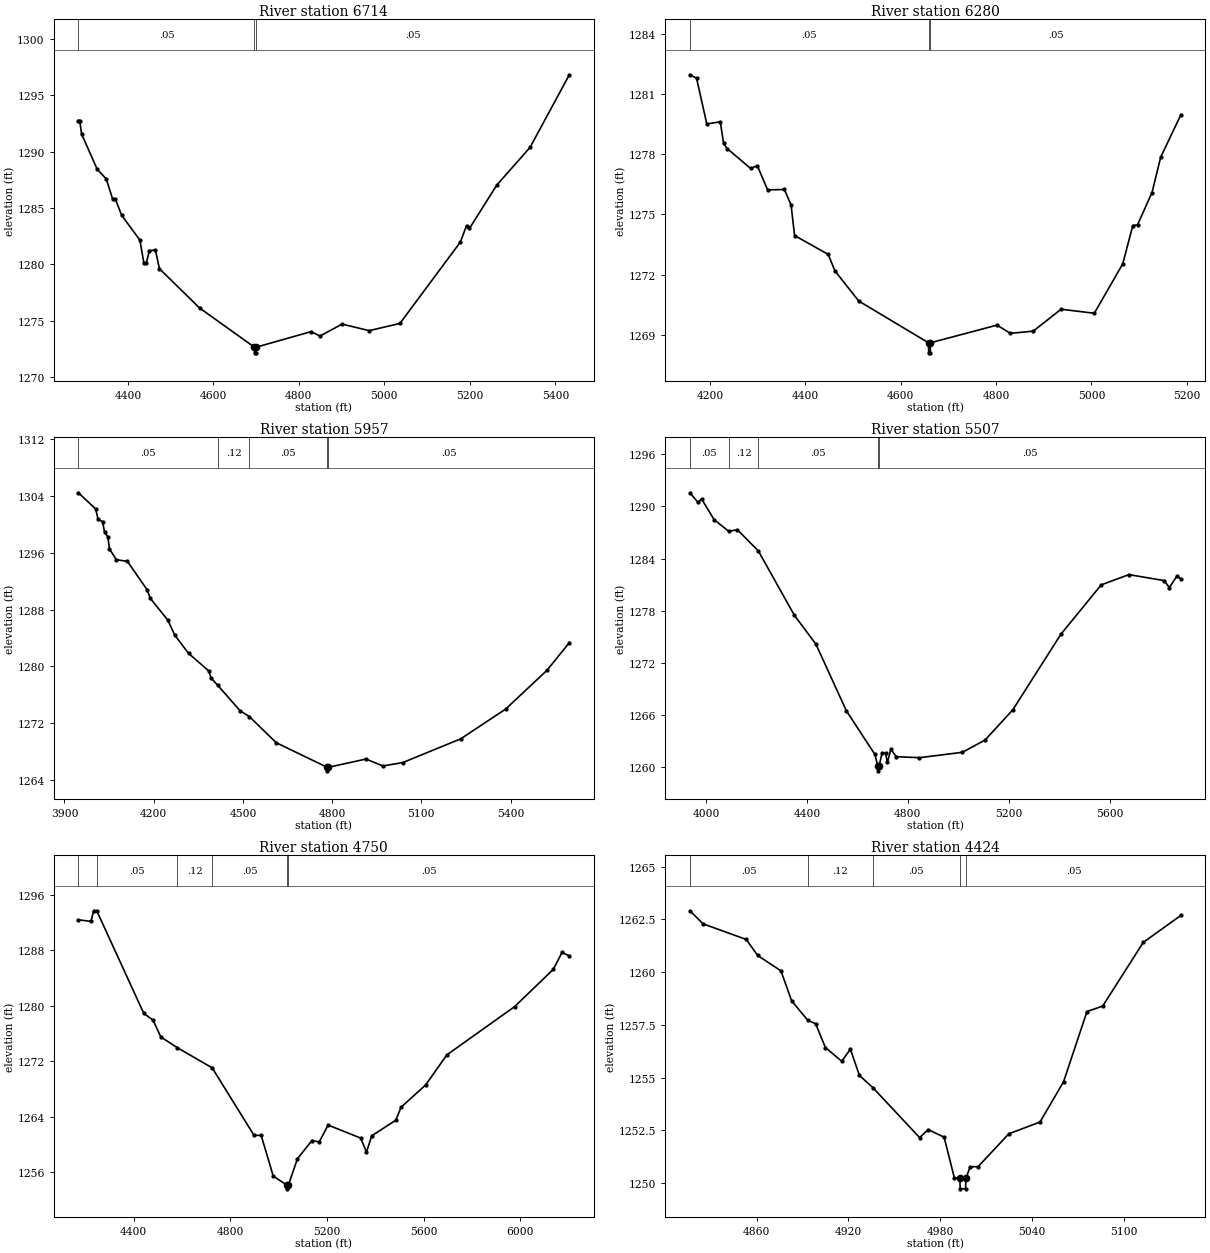
Type RM Length L Ch R = 1,6714,434,434,434
BEGIN DESCRIPTION:
LITTLE LLANO 038 14.0
END DESCRIPTION:
XS GIS Cut Line= 3
      2816205.67     10278953.10      2815820.50     10278350.00
      2815505.70     10278053.13
#Sta/Elev= 30
  4284.4 1292.77  4287.3 1292.77  4292.0 1291.56  4328.4 1288.44  4349.5 1287.59
  4364.7 1285.77  4370.7 1285.80  4385.9 1284.34  4428.2 1282.16  4437.5 1280.14
  4443.4 1280.14  4450.5 1281.22  4464.6 1281.27  4473.9 1279.62  4567.8 1276.13
  4696.1 1272.65  4696.3 1272.15  4699.8 1272.15  4700.1 1272.65  4828.4 1274.03
  4849.5 1273.64  4901.1 1274.70  4964.6 1274.12  5036.4 1274.76  5178.0 1281.99
  5192.2 1283.45  5199.1 1283.19  5263.0 1287.04  5340.7 1290.38  5432.7 1296.83
#Mann=3,-1,0
  4284.4    0.05       0  4696.1    0.03       0  4700.1    0.05       0
Bank Sta=4696.1,4700.1
Exp/Cntr=0.3,0.1

Type RM Length L Ch R = 1,6280,323,323,323
BEGIN DESCRIPTION:
LITTLE LLANO 038 13.0
END DESCRIPTION:
XS GIS Cut Line= 3
      2816655.67     10278553.10      2816041.75     10277977.00
      2815855.68     10277953.11
#Sta/Elev= 30
  4158.1 1281.95  4172.0 1281.78  4193.5 1279.50  4221.8 1279.61  4228.7 1278.53
  4236.0 1278.28  4285.3 1277.29  4299.5 1277.42  4321.0 1276.22  4356.2 1276.24
  4370.3 1275.46  4377.5 1273.95  4448.0 1273.01  4462.2 1272.19  4512.0 1270.69
  4658.4 1268.61  4658.7 1268.11  4662.2 1268.11  4662.4 1268.61  4802.1 1269.49
  4830.0 1269.08  4878.0 1269.19  4936.4 1270.28  5006.1 1270.08  5065.7 1272.54
  5086.8 1274.44  5096.9 1274.49  5127.1 1276.09  5145.3 1277.85  5187.6 1279.96
#Mann=3,-1,0
  4158.1    0.05       0  4658.4    0.03       0  4662.4    0.05       0
Bank Sta=4658.4,4662.4
Exp/Cntr=0.3,0.1

Type RM Length L Ch R = 1,5957,450,450,450
BEGIN DESCRIPTION:
LITTLE LLANO 038 12.0
END DESCRIPTION:
XS GIS Cut Line= 3
      2817196.02     10278160.85      2816381.41     10277795.42
      2815705.69     10277453.11
#Sta/Elev= 30
  3947.1 1304.47  4005.2 1302.18  4013.2 1300.73  4028.4 1300.41  4035.1 1298.91
  4046.1 1298.28  4051.6 1296.55  4074.7 1295.04  4111.9 1294.80  4178.4 1290.77
  4188.6 1289.60  4247.9 1286.50  4271.1 1284.39  4317.5 1281.83  4385.9 1279.33
  4392.5 1278.38  4415.9 1277.31  4490.6 1273.74  4522.1 1272.91  4612.0 1269.24
  4783.2 1265.77  4783.4 1265.27  4787.2 1265.77  4913.6 1266.93  4971.0 1265.96
  5037.8 1266.44  5232.7 1269.79  5383.0 1273.97  5522.2 1279.44  5597.4 1283.34
#Mann=5,-1,0
  3947.1    0.05       0  4415.9    0.12       0  4522.1    0.05       0
  4783.2    0.03       0  4787.2    0.05       0
Bank Sta=4783.2,4787.2
Exp/Cntr=0.3,0.1

Type RM Length L Ch R = 1,5507,757,757,757
BEGIN DESCRIPTION:
Mapping XS 266249da
END DESCRIPTION:
XS GIS Cut Line= 3
      2817184.61     10277909.60      2816522.39     10277295.87
      2815479.99     10277292.93
#Sta/Elev= 30
  3936.7 1291.55  3968.8 1290.44  3983.0 1290.84  4032.3 1288.47  4090.6 1287.12
  4124.7 1287.31  4208.0 1284.86  4350.9 1277.46  4436.0 1274.16  4556.2 1266.53
  4669.6 1261.49  4681.7 1260.11  4682.0 1259.61  4685.7 1260.11  4697.9 1261.62
  4712.1 1261.64  4718.9 1260.57  4733.1 1262.09  4754.1 1261.24  4846.3 1261.12
  5016.3 1261.74  5106.3 1263.15  5216.3 1266.63  5406.3 1275.29  5566.3 1280.97
  5676.3 1282.15  5816.3 1281.46  5836.3 1280.65  5866.3 1281.98  5882.0 1281.66
#Mann=5,-1,0
  3936.7    0.05       0  4090.6    0.12       0  4208.0    0.05       0
  4681.7    0.03       0  4685.7    0.05       0
Bank Sta=4681.7,4685.7
Exp/Cntr=0.3,0.1

Type RM Length L Ch R = 1,4750,326,326,326
BEGIN DESCRIPTION:
Mapping XS c2a2b1c6
END DESCRIPTION:
XS GIS Cut Line= 4
      2817005.74     10276417.37      2816449.93     10276588.68
      2815996.92     10276588.68      2815163.23     10277133.05
#Sta/Elev= 30
  4172.0 1292.37  4224.4 1292.14  4234.8 1293.67  4247.9 1293.67  4442.5 1278.87
  4480.4 1277.93  4513.1 1275.48  4580.3 1273.96  4725.4 1271.03  4897.9 1261.33
  4927.9 1261.29  4977.9 1255.43  5035.9 1254.10  5036.1 1253.60  5039.9 1254.10
  5077.9 1257.94  5137.9 1260.56  5167.9 1260.36  5204.7 1262.79  5339.5 1260.91
  5363.4 1258.87  5384.9 1261.24  5484.3 1263.48  5506.7 1265.37  5608.1 1268.57
  5695.6 1272.90  5976.1 1279.86  6136.0 1285.23  6172.2 1287.68  6202.3 1287.15
#Mann=6,-1,0
  4172.0    0.12       0  4247.9    0.05       0  4580.3    0.12       0
  4725.4    0.05       0  5035.9    0.05       0  5039.9    0.05       0
Bank Sta=5035.9,5039.9
Exp/Cntr=0.3,0.1

Type RM Length L Ch R = 1,4424,491,491,491
BEGIN DESCRIPTION:
LITTLE LLANO 038 9.0
END DESCRIPTION:
XS GIS Cut Line= 3
      2816355.68     10276353.11      2816190.00     10276274.00
      2816055.72     10276303.10
#Sta/Elev= 30
  4816.4 1262.91  4825.0 1262.29  4853.2 1261.55  4860.7 1260.79  4875.9 1260.06
  4882.9 1258.64  4893.4 1257.72  4898.6 1257.55  4905.0 1256.42  4915.7 1255.77
  4921.3 1256.35  4927.2 1255.10  4936.0 1254.52  4966.6 1252.15  4972.2 1252.53
  4982.6 1252.17  4989.3 1250.24  4992.9 1250.22  4993.1 1249.72  4996.6 1249.72
  4996.9 1250.22  4999.6 1250.77  5004.8 1250.77  5024.9 1252.33  5045.3 1252.89
  5060.7 1254.80  5076.0 1258.13  5086.3 1258.39  5112.8 1261.41  5137.4 1262.69
#Mann=5,-1,0
  4816.4    0.05       0  4893.4    0.12       0  4936.0    0.05       0
  4992.9    0.05       0  4996.9    0.05       0
Bank Sta=4992.9,4996.9
Exp/Cntr=0.3,0.1

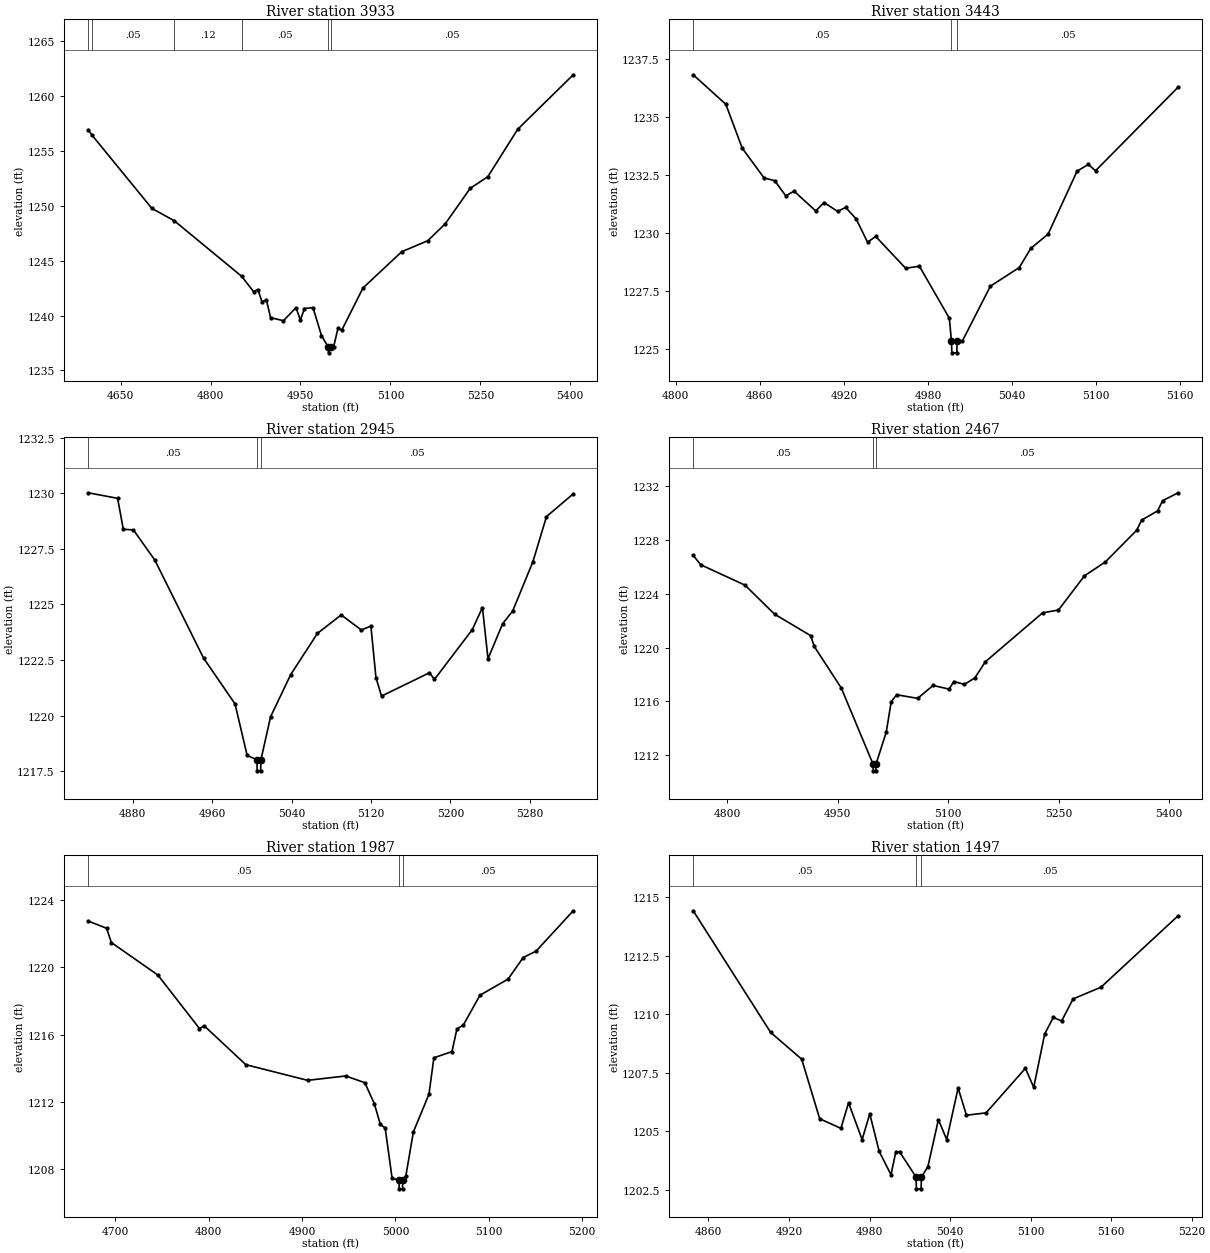
Type RM Length L Ch R = 1,3933,490,490,490
BEGIN DESCRIPTION:
LITTLE LLANO 038 8.0
END DESCRIPTION:
XS GIS Cut Line= 3
      2816455.70     10276153.13      2816178.75     10275859.00
      2815855.70     10276103.10
#Sta/Elev= 30
  4596.0 1256.94  4601.6 1256.50  4702.2 1249.77  4739.4 1248.65  4851.9 1243.58
  4871.7 1242.19  4879.0 1242.37  4885.9 1241.24  4893.2 1241.44  4900.1 1239.81
  4921.5 1239.53  4942.6 1240.72  4949.8 1239.59  4956.7 1240.64  4970.9 1240.73
  4985.0 1238.18  4996.6 1237.10  4996.8 1236.60  5000.6 1237.10  5005.1 1237.10
  5012.6 1238.85  5018.9 1238.67  5054.3 1242.52  5118.8 1245.82  5162.5 1246.83
  5191.6 1248.38  5233.2 1251.61  5262.4 1252.66  5312.3 1256.99  5404.9 1261.96
#Mann=6,-1,0
  4596.0    0.12       0  4601.6    0.05       0  4739.4    0.12       0
  4851.9    0.05       0  4996.6    0.05       0  5000.6    0.05       0
Bank Sta=4996.6,5000.6
Exp/Cntr=0.3,0.1

Type RM Length L Ch R = 1,3443,498,498,498
BEGIN DESCRIPTION:
LITTLE LLANO 038 7.0
END DESCRIPTION:
XS GIS Cut Line= 3
      2816455.66     10275603.08      2816359.50     10275442.00
      2816205.64     10275403.10
#Sta/Elev= 30
  4812.4 1236.82  4835.7 1235.55  4847.4 1233.66  4863.0 1232.38  4870.6 1232.26
  4878.5 1231.61  4884.4 1231.81  4899.9 1230.96  4905.8 1231.32  4915.5 1230.94
  4921.3 1231.11  4928.8 1230.61  4936.9 1229.61  4942.7 1229.86  4964.1 1228.49
  4973.9 1228.58  4995.3 1226.34  4996.8 1225.35  4997.1 1224.85  5000.6 1224.85
  5000.8 1225.35  5004.5 1225.35  5024.6 1227.72  5045.2 1228.52  5053.5 1229.35
  5065.8 1229.96  5086.5 1232.67  5094.5 1232.96  5099.7 1232.69  5158.7 1236.29
#Mann=3,-1,0
  4812.4    0.05       0  4996.8    0.05       0  5000.8    0.05       0
Bank Sta=4996.8,5000.8
Exp/Cntr=0.3,0.1

Type RM Length L Ch R = 1,2945,478,478,478
BEGIN DESCRIPTION:
LITTLE LLANO 038 6.0
END DESCRIPTION:
XS GIS Cut Line= 3
      2816605.70     10275153.15      2816524.25     10275010.00
      2816205.69     10274953.11
#Sta/Elev= 30
  4835.3 1230.02  4864.9 1229.77  4870.6 1228.38  4880.8 1228.35  4902.4 1226.99
  4951.4 1222.59  4983.1 1220.53  4995.3 1218.21  5005.2 1218.02  5005.4 1217.52
  5008.9 1217.52  5009.2 1218.02  5018.9 1219.95  5039.2 1221.85  5066.1 1223.70
  5090.0 1224.53  5110.3 1223.85  5119.9 1224.03  5125.0 1221.71  5130.6 1220.88
  5178.9 1221.93  5183.9 1221.63  5222.0 1223.87  5232.2 1224.86  5237.8 1222.56
  5252.5 1224.13  5262.7 1224.71  5283.0 1226.92  5296.7 1228.95  5323.6 1229.97
#Mann=3,-1,0
  4835.3    0.05       0  5005.2    0.05       0  5009.2    0.05       0
Bank Sta=5005.2,5009.2
Exp/Cntr=0.3,0.1

Type RM Length L Ch R = 1,2467,480,480,480
BEGIN DESCRIPTION:
LITTLE LLANO 038 5.0
END DESCRIPTION:
XS GIS Cut Line= 3
      2816855.69     10274903.15      2816833.00     10274658.00
      2816555.71     10274353.14
#Sta/Elev= 30
  4753.8 1226.87  4763.9 1226.17  4824.1 1224.65  4864.3 1222.49  4913.1 1220.90
  4918.1 1220.09  4954.7 1217.01  4997.9 1211.34  4998.2 1210.84  5001.7 1210.84
  5001.9 1211.34  5015.8 1213.71  5022.6 1215.99  5030.0 1216.50  5058.4 1216.23
  5079.4 1217.19  5101.0 1216.92  5107.7 1217.48  5121.9 1217.27  5136.1 1217.75
  5150.3 1218.95  5228.0 1222.59  5249.6 1222.80  5284.8 1225.34  5313.1 1226.37
  5355.7 1228.73  5362.5 1229.49  5384.1 1230.17  5390.9 1230.93  5412.1 1231.52
#Mann=3,-1,0
  4753.8    0.05       0  4997.9    0.05       0  5001.9    0.05       0
Bank Sta=4997.9,5001.9
Exp/Cntr=0.3,0.1

Type RM Length L Ch R = 1,1987,490,490,490
BEGIN DESCRIPTION:
LITTLE LLANO 038 4.0
END DESCRIPTION:
XS GIS Cut Line= 3
      2817105.69     10274703.09      2817173.75     10274381.00
      2817105.67     10274203.08
#Sta/Elev= 30
  4670.8 1222.75  4690.5 1222.32  4695.6 1221.47  4745.4 1219.54  4790.0 1216.36
  4795.1 1216.52  4839.7 1214.21  4905.9 1213.28  4946.7 1213.54  4967.2 1213.14
  4977.4 1211.89  4983.8 1210.66  4989.0 1210.45  4996.4 1207.47  5003.8 1207.33
  5004.1 1206.83  5007.6 1206.83  5007.8 1207.33  5011.2 1207.61  5019.2 1210.21
  5035.9 1212.45  5041.2 1214.62  5060.6 1214.99  5065.9 1216.34  5072.7 1216.56
  5090.6 1218.34  5120.7 1219.30  5136.9 1220.58  5150.7 1220.96  5190.5 1223.36
#Mann=3,-1,0
  4670.8    0.05       0  5003.8    0.05       0  5007.8    0.05       0
Bank Sta=5003.8,5007.8
Exp/Cntr=0.3,0.1

Type RM Length L Ch R = 1,1497,491,491,491
BEGIN DESCRIPTION:
LITTLE LLANO 038 3.0
END DESCRIPTION:
XS GIS Cut Line= 3
      2817705.70     10274503.14      2817630.25     10274372.00
      2817505.66     10274203.08
#Sta/Elev= 30
  4848.7 1214.41  4906.4 1209.22  4929.5 1208.08  4942.9 1205.54  4958.7 1205.13
  4964.4 1206.22  4974.5 1204.65  4980.2 1205.75  4987.2 1204.15  4996.0 1203.15
  4999.6 1204.13  5002.4 1204.13  5014.7 1203.05  5014.9 1202.55  5018.4 1202.55
  5018.7 1203.05  5023.5 1203.50  5031.3 1205.50  5037.5 1204.65  5046.0 1206.85
  5052.2 1205.69  5066.8 1205.79  5096.1 1207.69  5102.3 1206.88  5110.5 1209.16
  5116.9 1209.86  5123.1 1209.71  5131.6 1210.65  5152.4 1211.15  5209.9 1214.20
#Mann=3,-1,0
  4848.7    0.05       0  5014.7    0.03       0  5018.7    0.05       0
Bank Sta=5014.7,5018.7
Exp/Cntr=0.3,0.1

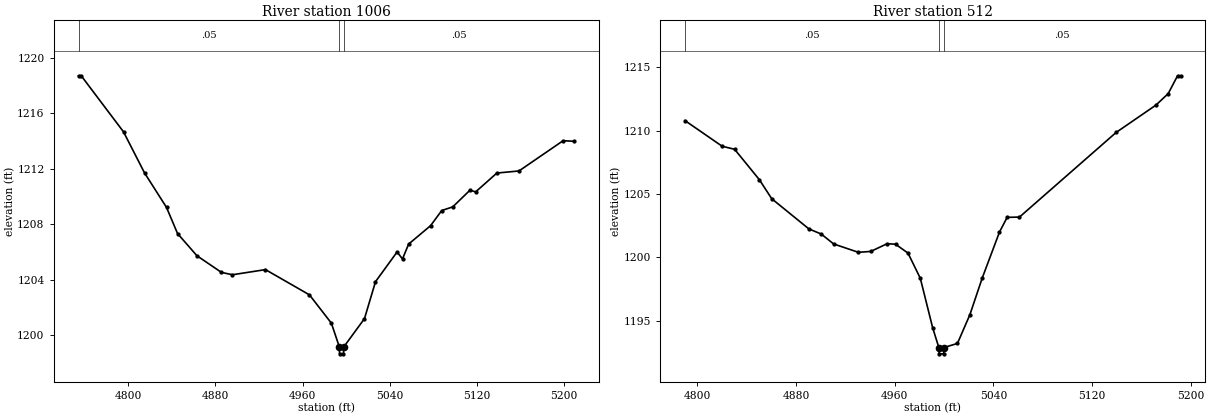
Type RM Length L Ch R = 1,1006,494,494,494
BEGIN DESCRIPTION:
LITTLE LLANO 038 2.0
END DESCRIPTION:
XS GIS Cut Line= 3
      2818005.71     10274103.11      2817762.25     10274070.00
      2817555.69     10274103.11
#Sta/Elev= 30
  4754.3 1218.71  4756.8 1218.71  4795.6 1214.67  4814.9 1211.71  4835.1 1209.22
  4845.2 1207.34  4863.0 1205.74  4885.5 1204.54  4895.6 1204.37  4925.9 1204.74
  4966.3 1202.92  4986.4 1200.88  4993.7 1199.17  4993.9 1198.67  4997.5 1198.67
  4997.8 1199.17  5016.8 1201.21  5026.9 1203.87  5046.7 1206.01  5051.7 1205.51
  5057.3 1206.58  5077.5 1207.91  5087.7 1209.00  5097.8 1209.26  5113.7 1210.47
  5118.8 1210.34  5138.3 1211.70  5158.6 1211.85  5199.1 1214.03  5209.2 1213.99
#Mann=3,-1,0
  4754.3    0.05       0  4993.7    0.05       0  4997.8    0.05       0
Bank Sta=4993.7,4997.8
Exp/Cntr=0.3,0.1

Type RM Length L Ch R = 1,512,0,0,0
BEGIN DESCRIPTION:
LITTLE LLANO 038 1.0
END DESCRIPTION:
XS GIS Cut Line= 3
      2818005.68     10273903.10      2817986.25     10273694.00
      2818005.69     10273503.09
#Sta/Elev= 30
  4790.0 1210.78  4820.1 1208.76  4830.2 1208.52  4850.2 1206.13  4860.3 1204.62
  4890.4 1202.24  4900.5 1201.83  4910.5 1201.05  4930.6 1200.39  4940.6 1200.46
  4953.9 1201.07  4960.7 1201.03  4970.8 1200.33  4980.8 1198.34  4990.8 1194.44
  4995.8 1192.88  4996.1 1192.38  4999.7 1192.38  5000.0 1192.88  5010.9 1193.20
  5021.0 1195.47  5031.0 1198.36  5045.0 1201.99  5051.2 1203.15  5061.2 1203.17
  5139.6 1209.85  5171.8 1212.00  5181.8 1212.91  5189.4 1214.32  5191.9 1214.32
#Mann=3,-1,0
  4790.0    0.05       0  4995.8    0.03       0  5000.0    0.05       0
Bank Sta=4995.8,5000
Exp/Cntr=0.3,0.1

Chan Stop Cuts=-1