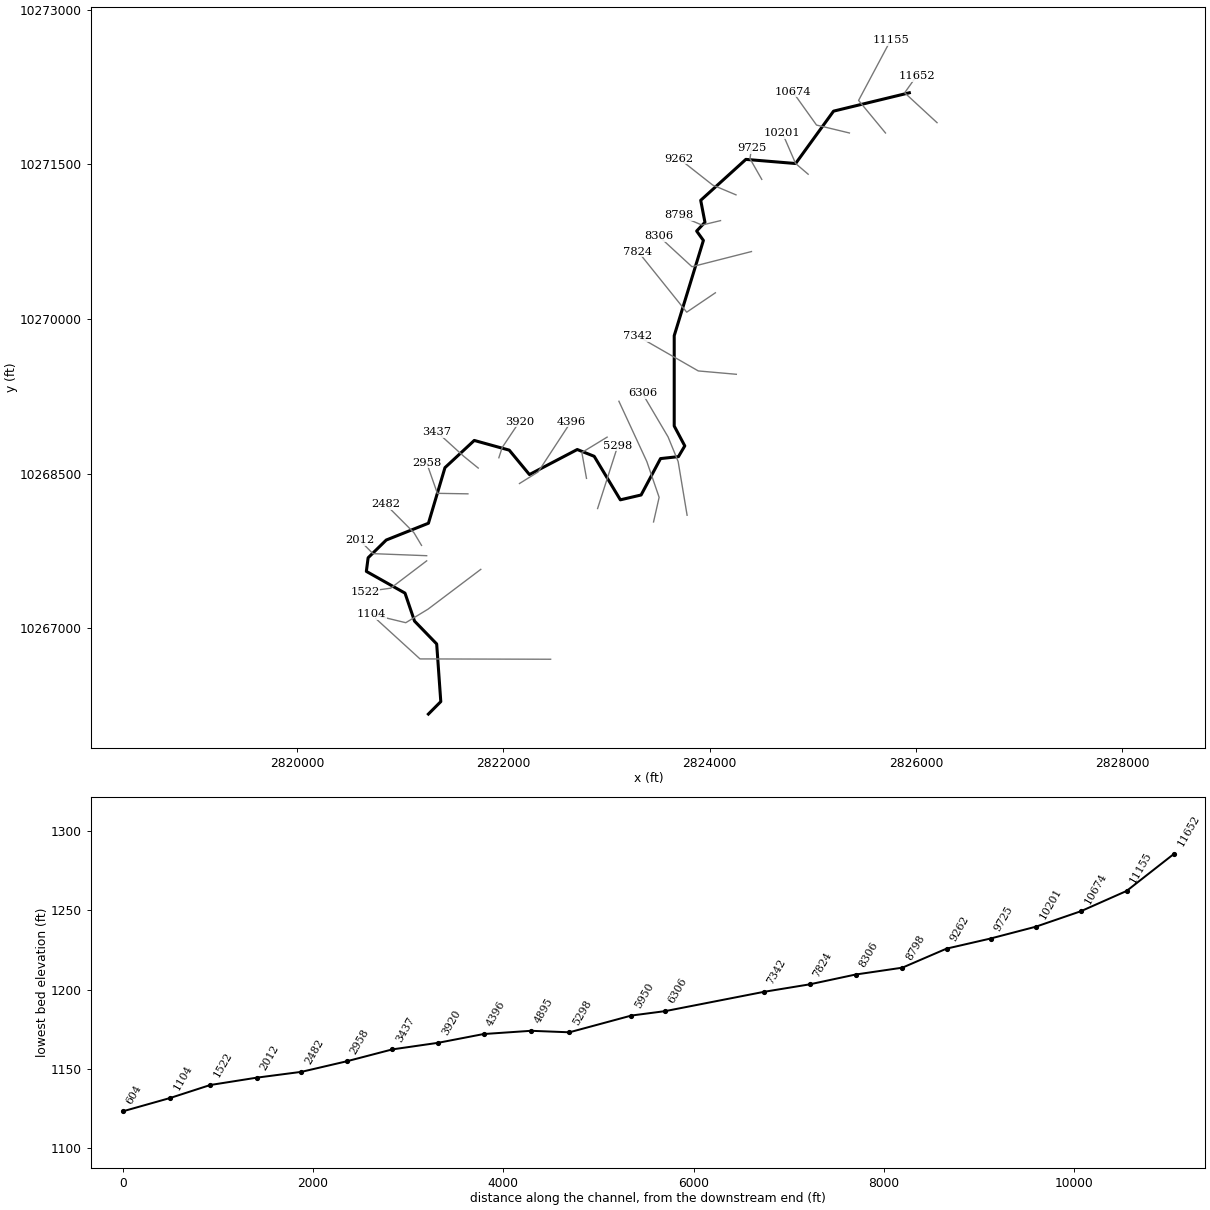
--- LITTLE LLANO 039.prj (project) ---

Proj Title=LITTLE LLANO 039 Base Level Engineering
Current Plan=p01
Default Exp/Contr=0.3,0.1
English Units
Geom File=g01
Flow File=f01
Plan File=p01
BEGIN DESCRIPTION:
LITTLE LLANO 039
END DESCRIPTION:

--- LITTLE LLANO 039.p01 (plan) ---

Plan Title=Multiple Run
Short Identifier=Multiple
Geom File=g01
Flow File=f01
Subcritical Flow
K Sum by GR= 0
Std Step Tol= 0.01
Critical Tol= 0.01
Num of Std Step Trials= 20
Max Error Tol= 0.3
Flow Tol Ratio= 0.001
Split Flow NTrial= 30
Split Flow Tol= 0.02
Split Flow Ratio= 0.02
Log Output Level= 0
Friction Slope Method= 1
Unsteady Friction Slope Method= 2
Unsteady Bridges Friction Slope Method= 1
Parabolic Critical Depth
Global Vel Dist=  1 , 1 , 1
Global Log Level= 0
CheckData=True
Encroach Param= -1, 0, 0, 0
BEGIN DESCRIPTION:
Multiple Run
END DESCRIPTION:

--- LITTLE LLANO 039.f01 (steady flow) ---

Flow Title=Multiple
Number of Profiles=7
Profile Names=10-year,25-year,50-year,1pct_min,100-year,1pct_plu,500-year
River Rch & RM= LITTLE LLANO 039,Reach-1,11652
     355     568     954     740    1303    2296    1860
River Rch & RM= LITTLE LLANO 039,Reach-1,3437
     703    1174    2073    1559    2897    5383    4098
River Rch & RM= LITTLE LLANO 039,Reach-1,1104
     761    1278    2278    1691    3196    6039    4531
Boundary for River Rch & Prof#=LITTLE LLANO 039,Reach-1,1
Up Type=0
Dn Type=3
Dn Slope=0.005
Boundary for River Rch & Prof#=LITTLE LLANO 039,Reach-1,2
Up Type=0
Dn Type=3
Dn Slope=0.005
Boundary for River Rch & Prof#=LITTLE LLANO 039,Reach-1,3
Up Type=0
Dn Type=3
Dn Slope=0.005
Boundary for River Rch & Prof#=LITTLE LLANO 039,Reach-1,4
Up Type=0
Dn Type=3
Dn Slope=0.005
Boundary for River Rch & Prof#=LITTLE LLANO 039,Reach-1,5
Up Type=0
Dn Type=3
Dn Slope=0.005
Boundary for River Rch & Prof#=LITTLE LLANO 039,Reach-1,6
Up Type=0
Dn Type=3
Dn Slope=0.005
Boundary for River Rch & Prof#=LITTLE LLANO 039,Reach-1,7
Up Type=0
Dn Type=3
Dn Slope=0.005

--- LITTLE LLANO 039.g01 (geometry) ---

Geom Title=Existing Conditions

River Reach=LITTLE LLANO 039,Reach-1
Reach XY= 30
      2825937.00     10272193.00      2825202.00     10272015.00
      2824834.00     10271507.00      2824351.25     10271547.00
      2823913.50     10271150.00      2823954.50     10270937.00
      2823874.00     10270852.00      2823939.50     10270761.00
      2823656.50     10269837.00      2823656.50     10268961.00
      2823759.00     10268768.00      2823697.50     10268664.00
      2823523.75     10268645.00      2823335.50     10268292.00
      2823134.00     10268245.00      2822880.50     10268667.00
      2822716.00     10268733.00      2822252.25     10268490.00
      2822056.50     10268727.00      2821717.25     10268821.00
      2821433.00     10268557.00      2821272.75     10268018.00
      2820863.25     10267855.00      2820687.75     10267683.00
      2820670.50     10267551.00      2821045.50     10267340.00
      2821137.75     10267069.00      2821352.75     10266847.00
      2821392.50     10266288.00      2821272.25     10266167.00

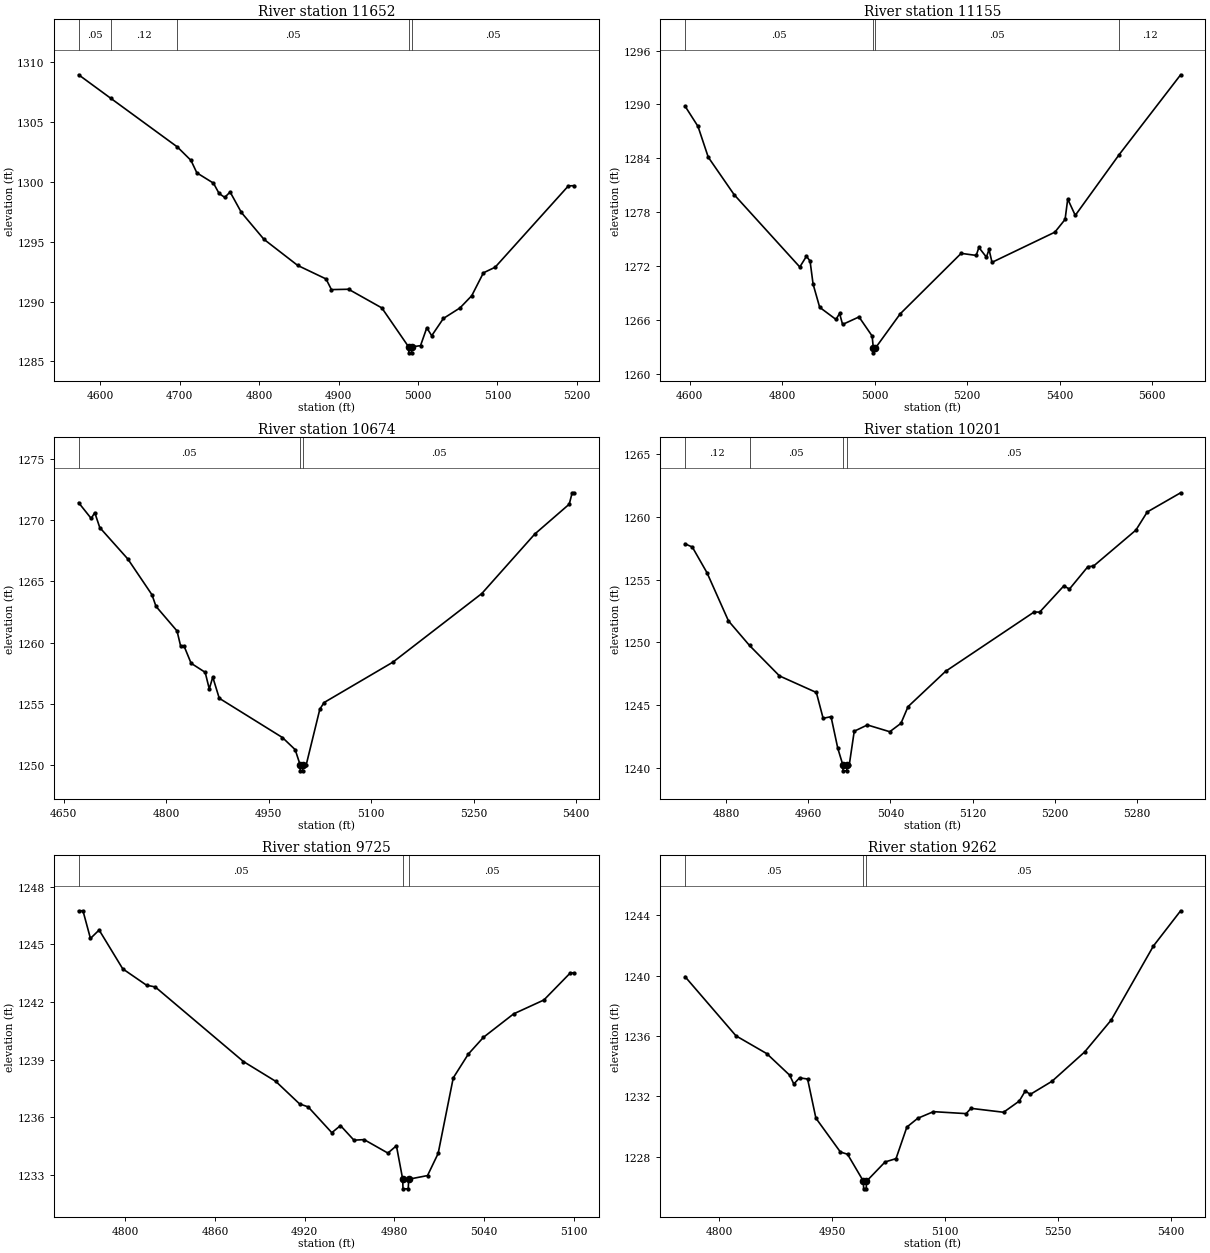
Type RM Length L Ch R = 1,11652,497,497,497
BEGIN DESCRIPTION:
LITTLE LLANO 039 23.0
END DESCRIPTION:
XS GIS Cut Line= 3
      2826205.69     10271903.10      2825891.50     10272193.00
      2826005.71     10272353.15
#Sta/Elev= 30
  4572.5 1308.94  4613.3 1306.96  4696.9 1302.91  4714.0 1301.79  4721.4 1300.75
  4742.3 1299.89  4749.4 1299.03  4756.5 1298.70  4763.3 1299.15  4777.5 1297.44
  4805.9 1295.20  4848.4 1293.02  4884.1 1291.89  4890.9 1291.00  4912.5 1291.03
  4954.4 1289.47  4988.1 1286.22  4988.4 1285.72  4991.9 1285.72  4992.1 1286.22
  5003.1 1286.32  5011.0 1287.81  5017.2 1287.15  5031.9 1288.59  5052.8 1289.47
  5067.6 1290.49  5082.3 1292.40  5097.1 1292.87  5189.3 1299.66  5196.7 1299.68
#Mann=5,-1,0
  4572.5    0.05       0  4613.3    0.12       0  4696.9    0.05       0
  4988.1    0.03       0  4992.1    0.05       0
Bank Sta=4988.1,4992.1
Exp/Cntr=0.3,0.1

Type RM Length L Ch R = 1,11155,481,481,481
BEGIN DESCRIPTION:
LITTLE LLANO 039 22.0
END DESCRIPTION:
XS GIS Cut Line= 3
      2825705.67     10271803.13      2825444.75     10272119.00
      2825755.68     10272703.10
#Sta/Elev= 30
  4590.3 1289.82  4618.3 1287.56  4640.5 1284.13  4696.4 1279.96  4838.4 1271.90
  4852.8 1273.10  4860.6 1272.56  4867.1 1270.00  4881.4 1267.41  4916.6 1266.06
  4924.4 1266.73  4930.9 1265.50  4966.4 1266.34  4994.8 1264.21  4997.4 1262.84
  4997.7 1262.34  5001.4 1262.84  5055.4 1266.68  5187.2 1273.42  5219.8 1273.19
  5225.5 1274.08  5241.8 1273.00  5247.5 1273.85  5253.9 1272.42  5389.8 1275.78
  5411.9 1277.20  5417.6 1279.47  5433.9 1277.65  5529.0 1284.43  5661.7 1293.31
#Mann=4,-1,0
  4590.3    0.05       0  4997.4    0.03       0  5001.4    0.05       0
  5529.0    0.12       0
Bank Sta=4997.4,5001.4
Exp/Cntr=0.3,0.1

Type RM Length L Ch R = 1,10674,473,473,473
BEGIN DESCRIPTION:
LITTLE LLANO 039 21.0
END DESCRIPTION:
XS GIS Cut Line= 3
      2825355.71     10271803.10      2825036.75     10271880.00
      2824805.70     10272203.09
#Sta/Elev= 30
  4671.9 1271.43  4690.3 1270.14  4695.5 1270.62  4702.8 1269.40  4743.9 1266.83
  4779.3 1263.90  4785.1 1262.96  4815.9 1260.95  4821.2 1259.71  4826.3 1259.70
  4836.5 1258.31  4857.1 1257.57  4863.1 1256.21  4868.2 1257.18  4877.7 1255.45
  4970.2 1252.24  4988.8 1251.25  4996.0 1250.02  4996.2 1249.52  4999.7 1249.52
  5000.0 1250.02  5005.0 1250.02  5024.9 1254.56  5031.1 1255.10  5131.8 1258.40
  5262.0 1264.01  5339.5 1268.87  5389.9 1271.31  5394.2 1272.24  5397.2 1272.24
#Mann=3,-1,0
  4671.9    0.05       0  4996.0    0.03       0  5000.0    0.05       0
Bank Sta=4996,5000
Exp/Cntr=0.3,0.1

Type RM Length L Ch R = 1,10201,476,476,476
BEGIN DESCRIPTION:
LITTLE LLANO 039 20.0
END DESCRIPTION:
XS GIS Cut Line= 3
      2824955.68     10271403.11      2824834.00     10271507.00
      2824705.69     10271803.09
#Sta/Elev= 30
  4840.0 1257.86  4847.1 1257.60  4861.4 1255.55  4882.3 1251.71  4902.8 1249.75
  4932.0 1247.32  4967.9 1246.00  4974.5 1243.94  4982.2 1244.07  4988.8 1241.54
  4993.6 1240.25  4993.9 1239.75  4997.4 1239.75  4997.6 1240.25  5000.0 1240.25
  5004.8 1242.91  5017.6 1243.41  5039.4 1242.87  5050.3 1243.54  5057.2 1244.87
  5093.8 1247.69  5180.0 1252.42  5185.4 1252.41  5208.9 1254.50  5214.4 1254.25
  5232.4 1256.04  5237.8 1256.08  5279.1 1258.95  5290.2 1260.40  5322.7 1261.93
#Mann=4,-1,0
  4840.0    0.12       0  4902.8    0.05       0  4993.6    0.03       0
  4997.6    0.05       0
Bank Sta=4993.6,4997.6
Exp/Cntr=0.3,0.1

Type RM Length L Ch R = 1,9725,463,463,463
BEGIN DESCRIPTION:
LITTLE LLANO 039 19.0
END DESCRIPTION:
XS GIS Cut Line= 3
      2824505.69     10271353.11      2824391.25     10271554.00
      2824405.69     10271653.15
#Sta/Elev= 30
  4768.8 1246.74  4771.7 1246.74  4776.7 1245.30  4782.5 1245.74  4798.3 1243.72
  4814.2 1242.87  4820.0 1242.78  4879.0 1238.90  4900.6 1237.87  4916.5 1236.70
  4922.3 1236.54  4938.1 1235.20  4943.9 1235.57  4952.9 1234.81  4959.7 1234.84
  4975.6 1234.14  4981.3 1234.52  4985.5 1232.78  4985.7 1232.28  4989.2 1232.28
  4989.5 1232.78  5002.1 1232.97  5009.2 1234.12  5019.3 1238.05  5029.4 1239.29
  5039.5 1240.16  5059.7 1241.38  5079.9 1242.10  5097.6 1243.51  5100.2 1243.51
#Mann=3,-1,0
  4768.8    0.05       0  4985.5    0.03       0  4989.5    0.05       0
Bank Sta=4985.5,4989.5
Exp/Cntr=0.3,0.1

Type RM Length L Ch R = 1,9262,464,464,464
BEGIN DESCRIPTION:
LITTLE LLANO 039 18.0
END DESCRIPTION:
XS GIS Cut Line= 3
      2824255.73     10271203.09      2824029.75     10271298.00
      2823705.71     10271553.09
#Sta/Elev= 30
  4754.9 1239.93  4822.5 1236.01  4863.4 1234.83  4893.8 1233.40  4899.2 1232.82
  4906.8 1233.23  4917.5 1233.15  4928.5 1230.56  4961.0 1228.32  4970.5 1228.17
  4991.6 1226.38  4991.8 1225.88  4995.3 1225.88  4995.6 1226.38  5020.3 1227.66
  5034.8 1227.88  5049.2 1229.97  5063.6 1230.55  5084.5 1230.99  5127.8 1230.86
  5134.2 1231.21  5177.5 1230.95  5198.3 1231.69  5206.4 1232.37  5212.8 1232.13
  5241.7 1233.00  5285.0 1234.94  5320.2 1237.05  5376.3 1241.96  5412.4 1244.29
#Mann=3,-1,0
  4754.9    0.05       0  4991.6    0.05       0  4995.6    0.05       0
Bank Sta=4991.6,4995.6
Exp/Cntr=0.3,0.1

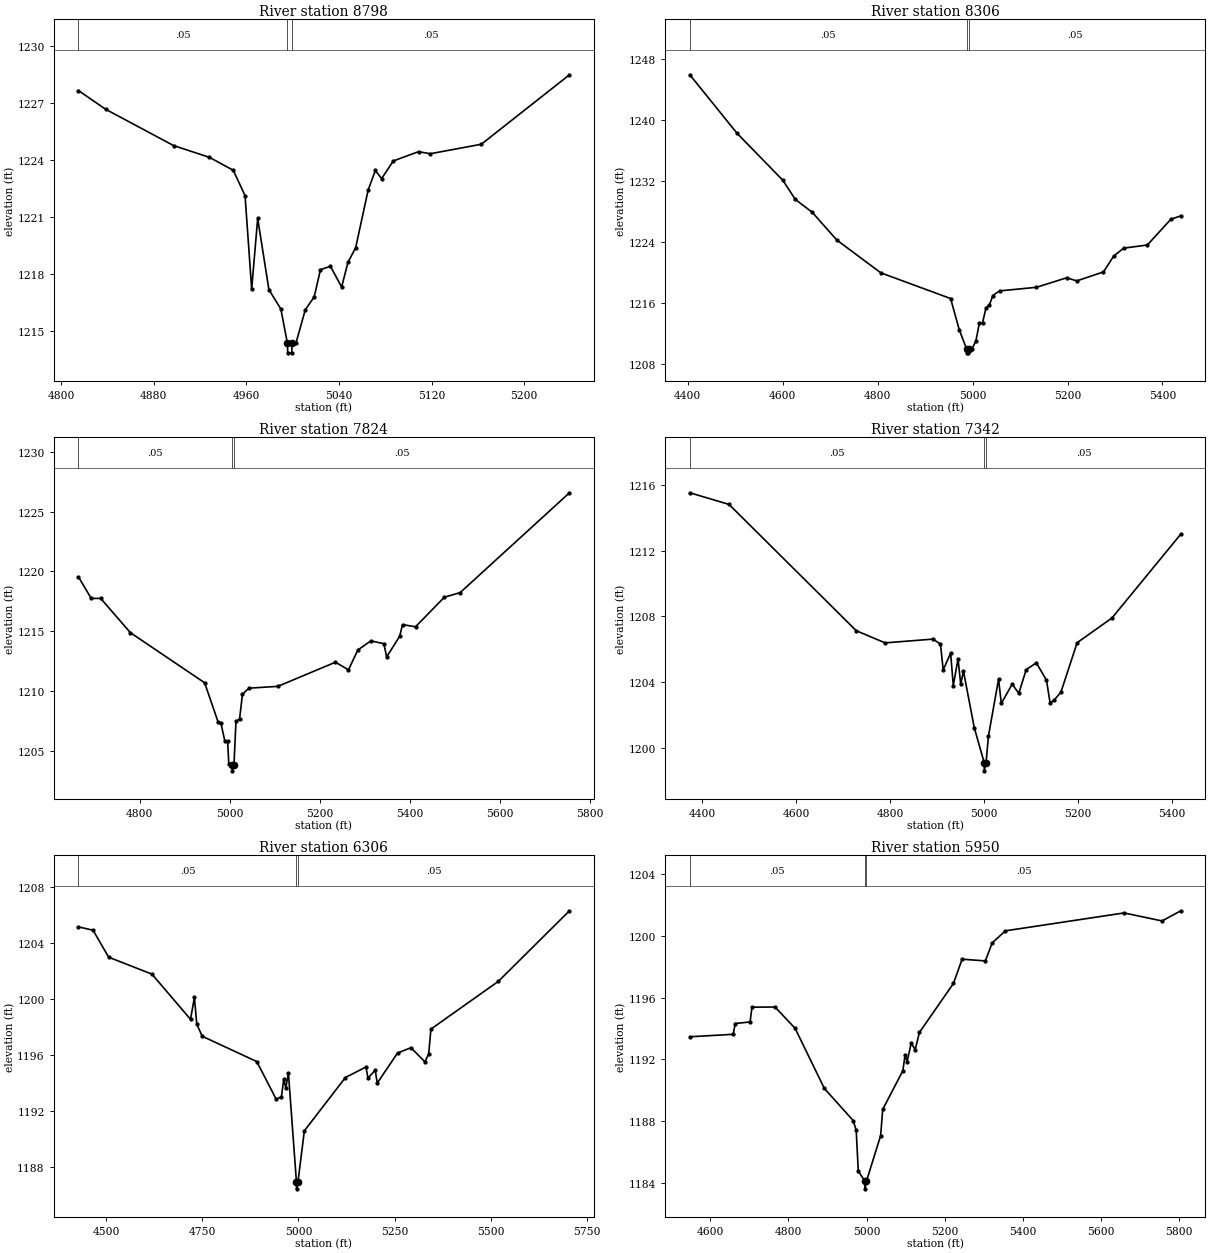
Type RM Length L Ch R = 1,8798,492,492,492
BEGIN DESCRIPTION:
LITTLE LLANO 039 17.0
END DESCRIPTION:
XS GIS Cut Line= 3
      2824105.66     10270953.11      2823925.75     10270910.00
      2823705.64     10271003.13
#Sta/Elev= 30
  4815.0 1227.68  4838.6 1226.69  4897.2 1224.78  4928.1 1224.16  4948.7 1223.48
  4958.9 1222.14  4964.6 1217.22  4969.8 1220.94  4979.5 1217.19  4989.8 1216.17
  4995.5 1214.36  4995.7 1213.86  4999.2 1213.86  4999.5 1214.36  5002.8 1214.36
  5010.9 1216.13  5018.6 1216.81  5024.0 1218.24  5032.6 1218.42  5042.3 1217.33
  5047.7 1218.62  5054.4 1219.40  5065.2 1222.44  5071.4 1223.47  5076.8 1223.04
  5086.9 1223.97  5108.7 1224.46  5118.8 1224.35  5162.9 1224.85  5239.0 1228.51
#Mann=3,-1,0
  4815.0    0.05       0  4995.5    0.03       0  4999.5    0.05       0
Bank Sta=4995.5,4999.5
Exp/Cntr=0.3,0.1

Type RM Length L Ch R = 1,8306,482,482,482
BEGIN DESCRIPTION:
LITTLE LLANO 039 16.0
END DESCRIPTION:
XS GIS Cut Line= 3
      2824405.65     10270653.10      2823828.50     10270506.00
      2823505.71     10270803.09
#Sta/Elev= 30
  4404.4 1245.88  4504.0 1238.22  4600.4 1232.08  4626.6 1229.58  4662.4 1227.89
  4714.0 1224.27  4806.8 1219.98  4953.7 1216.62  4971.9 1212.55  4987.4 1210.02
  4987.7 1209.52  4991.2 1209.52  4991.4 1210.02  4998.9 1210.07  5006.9 1211.05
  5014.3 1213.42  5021.0 1213.47  5028.4 1215.43  5035.2 1215.73  5042.6 1217.01
  5056.8 1217.62  5134.5 1218.09  5198.0 1219.33  5219.5 1218.93  5275.7 1220.10
  5297.2 1222.17  5318.2 1223.21  5368.1 1223.62  5417.5 1226.98  5438.7 1227.44
#Mann=3,-1,0
  4404.4    0.05       0  4987.4    0.05       0  4991.4    0.05       0
Bank Sta=4987.4,4991.4
Exp/Cntr=0.3,0.1

Type RM Length L Ch R = 1,7824,482,482,482
BEGIN DESCRIPTION:
LITTLE LLANO 039 15.0
END DESCRIPTION:
XS GIS Cut Line= 3
      2824055.68     10270253.11      2823777.75     10270065.00
      2823305.71     10270653.08
#Sta/Elev= 30
  4664.4 1219.55  4692.9 1217.74  4713.9 1217.74  4779.7 1214.88  4944.5 1210.69
  4974.5 1207.40  4980.5 1207.34  4989.4 1205.81  4995.5 1205.79  4998.2 1203.90
  5005.6 1203.83  5005.9 1203.33  5009.6 1203.83  5014.1 1207.48  5022.0 1207.64
  5028.4 1209.73  5042.8 1210.24  5106.9 1210.39  5234.9 1212.41  5263.7 1211.77
  5284.5 1213.43  5313.3 1214.19  5342.1 1213.96  5348.5 1212.85  5377.3 1214.58
  5383.7 1215.55  5412.5 1215.37  5476.5 1217.84  5511.7 1218.23  5754.1 1226.57
#Mann=3,-1,0
  4664.4    0.05       0  5005.6    0.03       0  5009.6    0.05       0
Bank Sta=5005.6,5009.6
Exp/Cntr=0.3,0.1

Type RM Length L Ch R = 1,7342,1036,1036,1036
BEGIN DESCRIPTION:
Mapping XS bd9e73d4
END DESCRIPTION:
XS GIS Cut Line= 3
      2824258.87     10269462.66      2823889.99     10269495.20
      2823304.09     10269831.56
#Sta/Elev= 30
  4373.3 1215.55  4456.8 1214.84  4727.9 1207.13  4789.3 1206.39  4891.4 1206.62
  4907.2 1206.31  4913.0 1204.74  4928.8 1205.76  4934.5 1203.78  4944.6 1205.42
  4950.3 1203.86  4956.1 1204.67  4979.2 1201.21  5000.3 1199.08  5000.5 1198.58
  5004.3 1199.08  5009.3 1200.69  5030.9 1204.17  5036.8 1202.69  5059.9 1203.87
  5074.0 1203.31  5089.8 1204.76  5111.4 1205.17  5133.0 1204.11  5140.6 1202.73
  5148.8 1202.88  5163.7 1203.38  5198.3 1206.40  5272.5 1207.91  5419.2 1213.03
#Mann=3,-1,0
  4373.3    0.05       0  5000.3    0.05       0  5004.3    0.05       0
Bank Sta=5000.3,5004.3
Exp/Cntr=0.3,0.1

Type RM Length L Ch R = 1,6306,356,356,356
BEGIN DESCRIPTION:
Mapping XS 8c7d818e
END DESCRIPTION:
XS GIS Cut Line= 4
      2823781.48     10268095.49      2823694.67     10268616.30
      2823597.02     10268855.01      2823347.45     10269278.19
#Sta/Elev= 30
  4427.7 1205.14  4465.8 1204.90  4506.4 1202.97  4619.0 1201.76  4719.3 1198.53
  4729.4 1200.09  4735.6 1198.18  4749.7 1197.32  4891.6 1195.51  4942.3 1192.81
  4955.7 1192.99  4961.9 1194.27  4967.3 1193.62  4973.9 1194.71  4994.8 1186.91
  4995.0 1186.41  4998.8 1186.91  5015.4 1190.56  5122.2 1194.37  5175.6 1195.12
  5181.0 1194.32  5199.6 1194.90  5205.0 1193.97  5257.8 1196.12  5292.7 1196.50
  5328.9 1195.49  5338.7 1196.05  5344.6 1197.83  5520.2 1201.25  5704.9 1206.29
#Mann=3,-1,0
  4427.7    0.05       0  4994.8    0.05       0  4998.8    0.05       0
Bank Sta=4994.8,4998.8
Exp/Cntr=0.3,0.1

Type RM Length L Ch R = 1,5950,652,652,652
BEGIN DESCRIPTION:
Mapping XS eae50933
END DESCRIPTION:
XS GIS Cut Line= 4
      2823455.97     10268030.39      2823510.21     10268269.08
      2823390.85     10268616.30      2823120.14     10269201.04
#Sta/Elev= 30
  4547.9 1193.47  4658.9 1193.63  4664.0 1194.33  4702.0 1194.43  4707.1 1195.39
  4766.0 1195.40  4817.4 1194.01  4892.1 1190.12  4966.1 1188.03  4973.6 1187.40
  4978.9 1184.76  4995.8 1184.11  4996.1 1183.61  4999.8 1184.11  5036.1 1187.06
  5041.4 1188.76  5093.0 1191.27  5098.6 1192.29  5103.9 1191.86  5114.2 1193.05
  5124.5 1192.64  5135.3 1193.75  5222.4 1196.93  5244.5 1198.50  5304.1 1198.39
  5321.5 1199.56  5355.4 1200.34  5658.9 1201.50  5756.1 1200.98  5804.2 1201.64
#Mann=3,-1,0
  4547.9    0.05       0  4995.8    0.03       0  4999.8    0.05       0
Bank Sta=4995.8,4999.8
Exp/Cntr=0.3,0.1

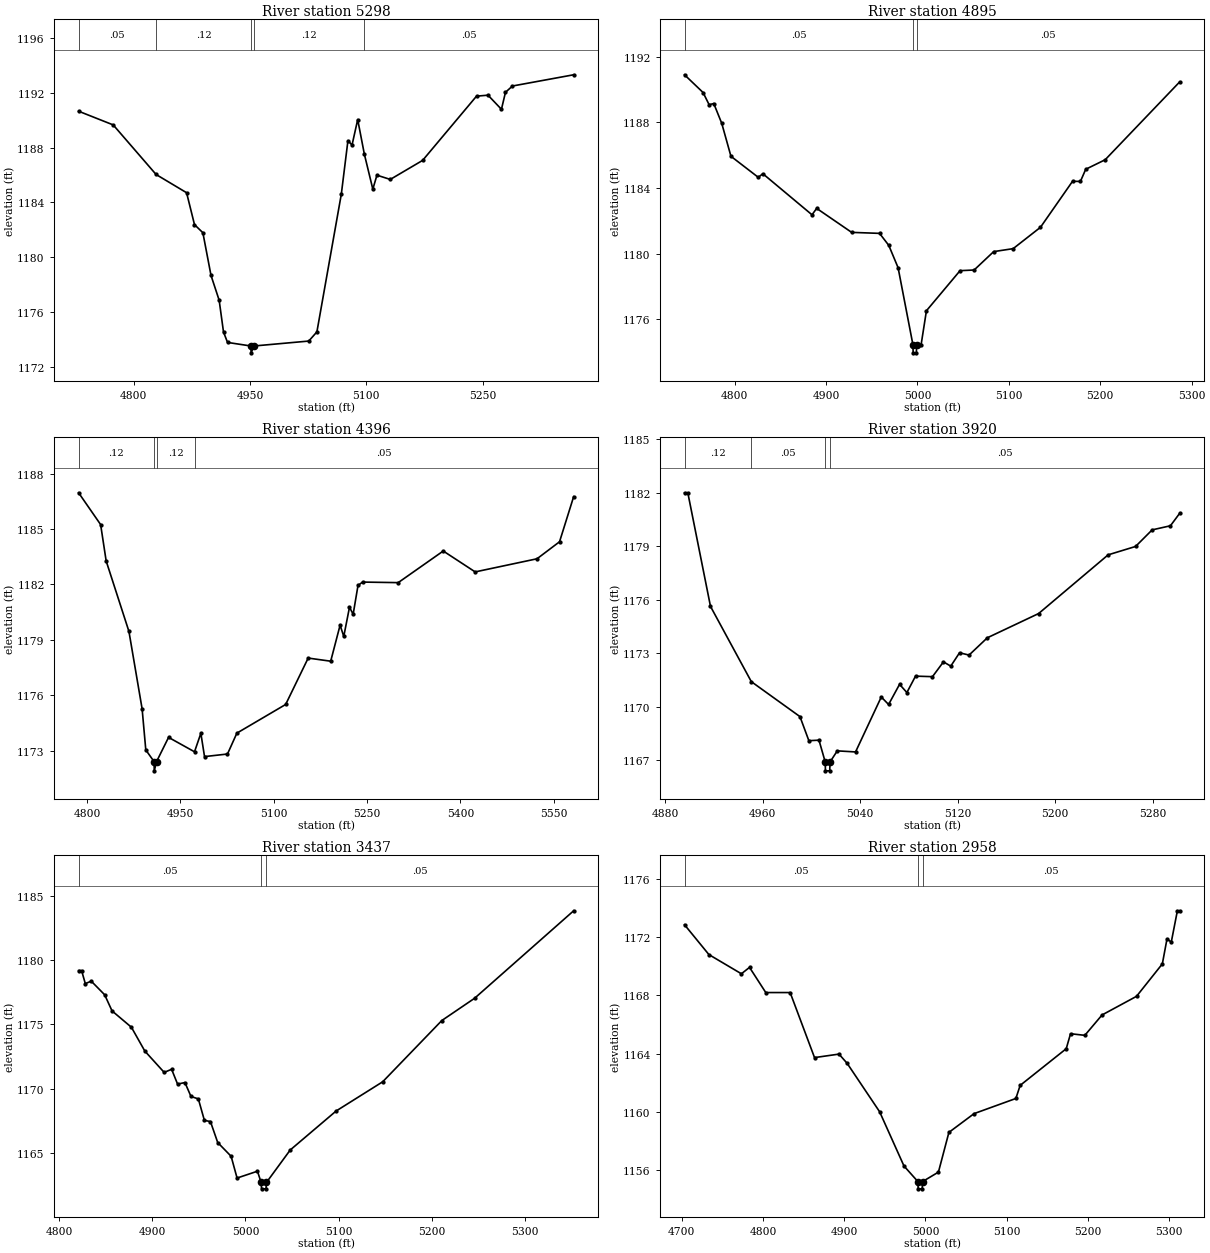
Type RM Length L Ch R = 1,5298,403,403,403
BEGIN DESCRIPTION:
Mapping XS 661a7f82
END DESCRIPTION:
XS GIS Cut Line= 2
      2822913.44     10268160.61      2823108.73     10268768.20
#Sta/Elev= 30
  4729.1 1190.66  4773.7 1189.66  4829.0 1186.04  4868.3 1184.71  4878.5 1182.38
  4889.3 1181.79  4899.8 1178.67  4910.3 1176.86  4915.9 1174.54  4921.1 1173.78
  4951.2 1173.52  4951.5 1173.02  4955.2 1173.52  5025.8 1173.88  5036.3 1174.55
  5067.8 1184.61  5076.3 1188.51  5081.6 1188.19  5088.9 1190.05  5097.5 1187.52
  5108.4 1184.97  5113.7 1185.99  5130.9 1185.68  5172.6 1187.07  5242.1 1191.76
  5256.9 1191.83  5274.2 1190.80  5279.4 1192.04  5288.4 1192.50  5367.3 1193.32
#Mann=5,-1,0
  4729.1    0.05       0  4829.0    0.12       0  4951.2    0.07       0
  4955.2    0.12       0  5097.5    0.05       0
Bank Sta=4951.2,4955.2
Exp/Cntr=0.3,0.1

Type RM Length L Ch R = 1,4895,499,499,499
BEGIN DESCRIPTION:
LITTLE LLANO 039 9.0
END DESCRIPTION:
XS GIS Cut Line= 3
      2822805.69     10268453.09      2822760.75     10268704.00
      2823005.72     10268853.14
#Sta/Elev= 30
  4745.1 1190.89  4765.4 1189.81  4772.0 1189.07  4777.1 1189.14  4785.8 1187.94
  4795.9 1185.93  4825.8 1184.65  4830.8 1184.87  4884.6 1182.37  4889.7 1182.76
  4928.0 1181.30  4958.5 1181.24  4968.6 1180.51  4978.8 1179.15  4995.0 1174.47
  4995.3 1173.97  4998.8 1173.97  4999.0 1174.47  5004.0 1174.47  5009.8 1176.53
  5046.6 1178.97  5062.0 1179.01  5083.4 1180.13  5104.7 1180.31  5134.6 1181.61
  5169.7 1184.41  5178.3 1184.40  5184.1 1185.14  5205.4 1185.72  5286.8 1190.45
#Mann=3,-1,0
  4745.1    0.05       0  4995.0    0.03       0  4999.0    0.05       0
Bank Sta=4995,4999
Exp/Cntr=0.3,0.1

Type RM Length L Ch R = 1,4396,476,476,476
BEGIN DESCRIPTION:
LITTLE LLANO 039 8.0
END DESCRIPTION:
XS GIS Cut Line= 3
      2822155.67     10268403.10      2822337.00     10268516.00
      2822655.69     10269003.11
#Sta/Elev= 30
  4786.4 1186.96  4821.8 1185.24  4830.7 1183.27  4867.3 1179.46  4888.5 1175.27
  4894.4 1173.05  4907.7 1172.42  4908.0 1171.92  4911.7 1172.42  4931.0 1173.73
  4972.7 1172.95  4982.9 1173.95  4988.8 1172.69  5025.7 1172.83  5040.8 1173.96
  5119.2 1175.51  5155.4 1178.02  5191.6 1177.85  5206.7 1179.80  5212.6 1179.19
  5221.8 1180.77  5227.7 1180.39  5235.5 1181.95  5242.9 1182.13  5300.1 1182.10
  5372.5 1183.81  5423.8 1182.68  5523.2 1183.39  5559.4 1184.31  5582.1 1186.75
#Mann=4,-1,0
  4786.4    0.12       0  4907.7    0.03       0  4911.7    0.12       0
  4972.7    0.05       0
Bank Sta=4907.7,4911.7
Exp/Cntr=0.3,0.1

Type RM Length L Ch R = 1,3920,483,483,483
BEGIN DESCRIPTION:
LITTLE LLANO 039 7.0
END DESCRIPTION:
XS GIS Cut Line= 3
      2821955.67     10268653.07      2821987.75     10268752.00
      2822155.69     10269003.12
#Sta/Elev= 30
  4896.0 1181.99  4898.7 1181.99  4917.3 1175.62  4950.8 1171.40  4990.7 1169.44
  4998.0 1168.09  5006.3 1168.12  5011.4 1166.90  5011.6 1166.40  5015.1 1166.40
  5015.4 1166.90  5021.3 1167.52  5036.3 1167.46  5057.4 1170.54  5063.4 1170.12
  5072.4 1171.25  5078.4 1170.79  5085.5 1171.71  5099.4 1171.68  5108.4 1172.51
  5114.4 1172.27  5121.6 1173.02  5129.4 1172.89  5144.4 1173.86  5186.5 1175.22
  5243.5 1178.51  5266.0 1178.98  5279.6 1179.91  5294.6 1180.14  5302.1 1180.83
#Mann=4,-1,0
  4896.0    0.12       0  4950.8    0.05       0  5011.4    0.05       0
  5015.4    0.05       0
Bank Sta=5011.4,5015.4
Exp/Cntr=0.3,0.1

Type RM Length L Ch R = 1,3437,479,479,479
BEGIN DESCRIPTION:
LITTLE LLANO 039 6.0
END DESCRIPTION:
XS GIS Cut Line= 3
      2821755.68     10268553.12      2821616.50     10268666.00
      2821355.67     10268903.12
#Sta/Elev= 30
  4820.8 1179.18  4824.0 1179.18  4828.0 1178.17  4834.4 1178.36  4848.8 1177.30
  4856.7 1176.05  4877.5 1174.78  4891.9 1172.93  4912.7 1171.27  4920.7 1171.51
  4927.1 1170.36  4935.0 1170.48  4941.5 1169.40  4949.4 1169.21  4955.9 1167.54
  4962.4 1167.45  4970.2 1165.82  4984.6 1164.75  4991.0 1163.06  5012.9 1163.59
  5016.8 1162.72  5017.3 1162.22  5022.1 1162.22  5022.6 1162.72  5048.1 1165.24
  5097.4 1168.27  5147.4 1170.54  5210.9 1175.30  5246.1 1177.03  5352.5 1183.83
#Mann=3,-1,0
  4820.8    0.05       0  5016.8    0.05       0  5022.6    0.05       0
Bank Sta=5016.8,5022.6
Exp/Cntr=0.3,0.1

Type RM Length L Ch R = 1,2958,476,476,476
BEGIN DESCRIPTION:
LITTLE LLANO 039 5.0
END DESCRIPTION:
XS GIS Cut Line= 3
      2821655.71     10268303.11      2821359.25     10268308.00
      2821255.67     10268603.15
#Sta/Elev= 30
  4703.5 1172.86  4733.5 1170.81  4773.5 1169.49  4783.5 1169.93  4803.5 1168.20
  4833.5 1168.20  4863.5 1163.73  4893.6 1163.97  4903.6 1163.34  4943.6 1160.01
  4973.6 1156.28  4990.7 1155.21  4991.1 1154.71  4996.0 1154.71  4996.5 1155.21
  5016.0 1155.86  5028.9 1158.59  5059.9 1159.88  5111.3 1160.92  5116.6 1161.82
  5173.3 1164.34  5178.6 1165.37  5196.2 1165.26  5217.4 1166.66  5259.8 1167.94
  5291.6 1170.17  5297.3 1171.88  5302.6 1171.67  5310.1 1173.82  5312.8 1173.82
#Mann=3,-1,0
  4703.5    0.05       0  4990.7    0.05       0  4996.5    0.05       0
Bank Sta=4990.7,4996.5
Exp/Cntr=0.3,0.1

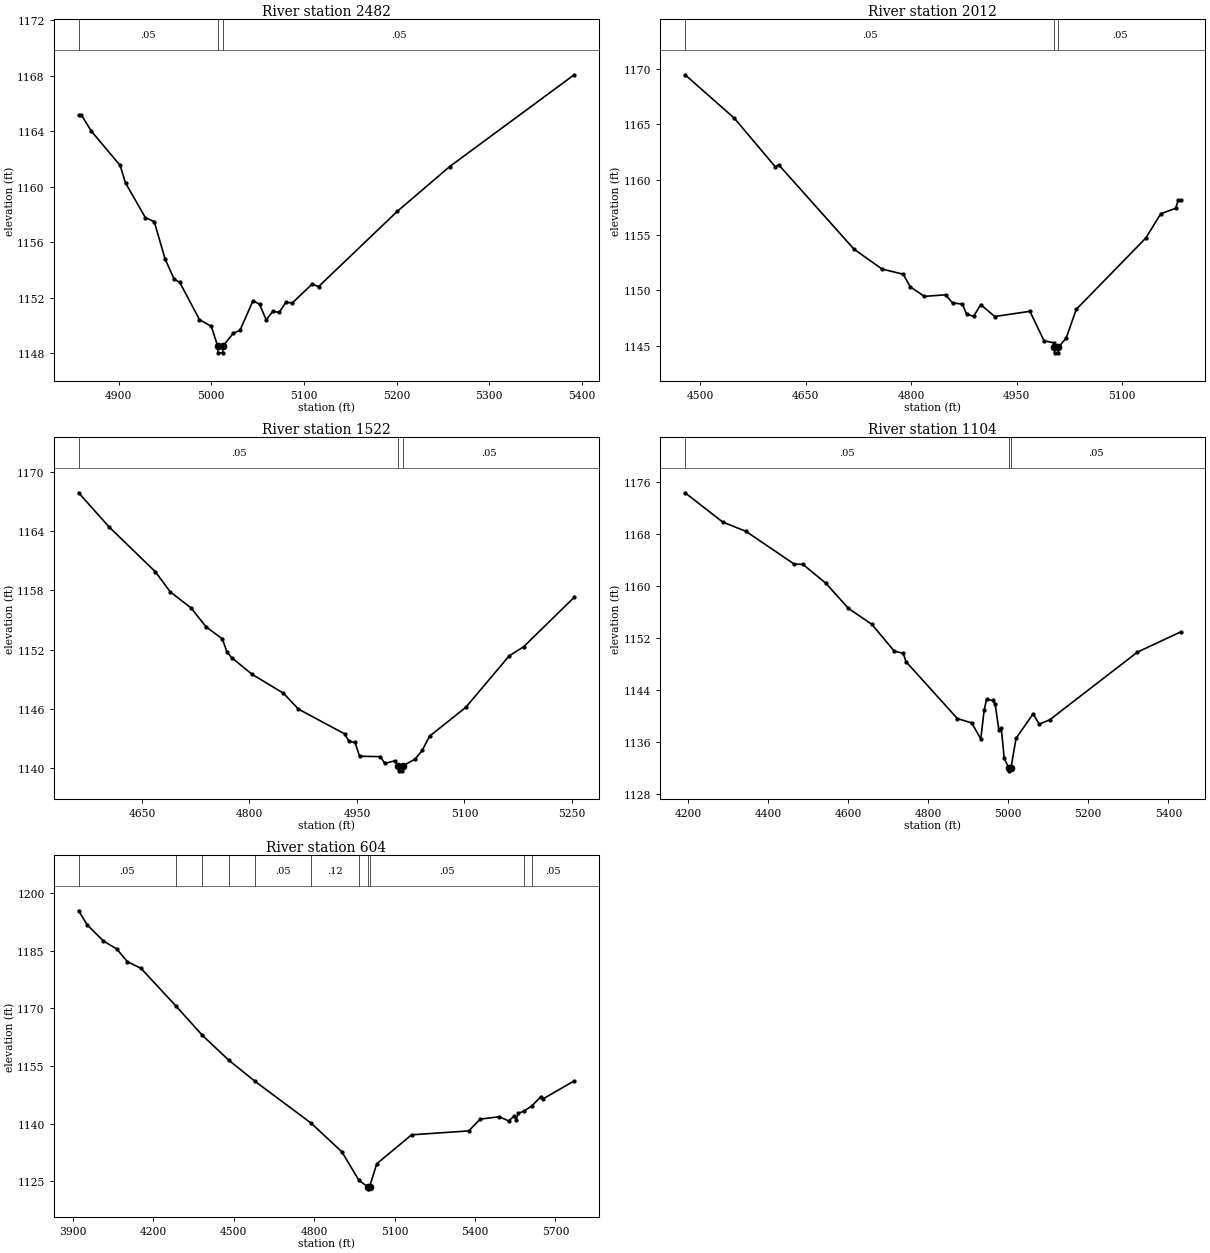
Type RM Length L Ch R = 1,2482,470,470,470
BEGIN DESCRIPTION:
LITTLE LLANO 039 4.0
END DESCRIPTION:
XS GIS Cut Line= 3
      2821205.71     10267803.08      2821132.25     10267926.00
      2820855.69     10268203.11
#Sta/Elev= 30
  4856.8 1165.17  4859.8 1165.17  4870.5 1164.01  4901.6 1161.54  4907.4 1160.28
  4928.8 1157.78  4938.4 1157.49  4950.2 1154.78  4960.0 1153.33  4965.8 1153.13
  4987.2 1150.43  5000.0 1149.95  5006.7 1148.54  5007.2 1148.04  5012.1 1148.04
  5012.6 1148.54  5023.8 1149.46  5030.9 1149.66  5045.0 1151.80  5052.1 1151.53
  5059.2 1150.41  5066.2 1151.02  5073.3 1150.96  5080.4 1151.67  5087.5 1151.64
  5108.7 1152.99  5115.7 1152.81  5200.6 1158.23  5257.2 1161.46  5391.5 1168.07
#Mann=3,-1,0
  4856.8    0.05       0  5006.7    0.05       0  5012.6    0.05       0
Bank Sta=5006.7,5012.6
Exp/Cntr=0.3,0.1

Type RM Length L Ch R = 1,2012,490,490,490
BEGIN DESCRIPTION:
LITTLE LLANO 039 3.0
END DESCRIPTION:
XS GIS Cut Line= 3
      2821255.67     10267703.11      2820734.75     10267723.00
      2820605.66     10267853.13
#Sta/Elev= 30
  4478.7 1169.47  4548.7 1165.55  4606.8 1161.17  4611.8 1161.34  4718.9 1153.72
  4758.9 1151.92  4788.9 1151.46  4798.9 1150.32  4818.9 1149.46  4849.0 1149.60
  4859.0 1148.87  4872.9 1148.76  4879.0 1147.85  4889.0 1147.66  4899.0 1148.72
  4919.0 1147.64  4969.0 1148.11  4989.1 1145.44  5002.9 1145.27  5003.5 1144.86
  5004.0 1144.36  5009.0 1144.36  5009.4 1144.86  5020.6 1145.70  5034.8 1148.28
  5133.8 1154.73  5155.0 1156.92  5176.2 1157.41  5179.7 1158.12  5183.3 1158.12
#Mann=3,-1,0
  4478.7    0.05       0  5003.5    0.05       0  5009.4    0.05       0
Bank Sta=5003.5,5009.4
Exp/Cntr=0.3,0.1

Type RM Length L Ch R = 1,1522,418,418,418
BEGIN DESCRIPTION:
LITTLE LLANO 039 2.0
END DESCRIPTION:
XS GIS Cut Line= 3
      2821255.67     10267653.10      2820906.50     10267388.00
      2820655.71     10267353.12
#Sta/Elev= 30
  4561.6 1167.90  4604.2 1164.43  4668.7 1159.89  4689.5 1157.85  4718.5 1156.22
  4739.4 1154.31  4762.2 1153.08  4768.5 1151.77  4775.0 1151.19  4803.9 1149.48
  4847.5 1147.57  4868.4 1145.96  4932.8 1143.45  4939.1 1142.68  4947.4 1142.58
  4953.6 1141.18  4982.7 1141.14  4989.0 1140.45  5002.9 1140.72  5007.9 1140.20
  5008.4 1139.70  5013.4 1139.70  5013.9 1140.20  5031.1 1140.88  5041.2 1141.78
  5051.3 1143.21  5101.8 1146.13  5162.4 1151.35  5182.6 1152.28  5253.2 1157.30
#Mann=3,-1,0
  4561.6    0.05       0  5007.9    0.03       0  5013.9    0.05       0
Bank Sta=5007.9,5013.9
Exp/Cntr=0.3,0.1

Type RM Length L Ch R = 1,1104,500,500,500
BEGIN DESCRIPTION:
Mapping XS d6002bb2
END DESCRIPTION:
XS GIS Cut Line= 4
      2821780.50     10267570.69      2821269.30     10267184.94
      2821052.90     10267053.22      2820718.97     10267134.36
#Sta/Elev= 30
  4193.2 1174.40  4286.9 1169.90  4345.1 1168.46  4465.8 1163.41  4487.4 1163.38
  4544.9 1160.45  4601.2 1156.58  4659.4 1154.14  4715.6 1150.00  4737.9 1149.66
  4744.8 1148.38  4873.0 1139.62  4909.2 1138.93  4931.5 1136.46  4940.1 1140.99
  4946.0 1142.56  4961.5 1142.40  4967.3 1141.87  4976.9 1137.81  4982.8 1138.13
  4990.0 1133.52  5001.1 1132.06  5001.6 1131.56  5007.1 1132.06  5019.6 1136.57
  5062.2 1140.34  5077.7 1138.76  5103.6 1139.42  5322.7 1149.85  5430.6 1152.96
#Mann=3,-1,0
  4193.2    0.05       0  5001.1    0.03       0  5007.1    0.05       0
Bank Sta=5001.1,5007.1
Exp/Cntr=0.3,0.1

Type RM Length L Ch R = 1,604,0,0,0
BEGIN DESCRIPTION:
LITTLE LLANO 039 1.0
END DESCRIPTION:
XS GIS Cut Line= 3
      2822457.93     10266698.82      2821190.89     10266701.96
      2820761.21     10267094.01
#Sta/Elev= 30
  3921.3 1195.35  3953.5 1191.68  4013.5 1187.50  4063.5 1185.43  4103.5 1182.09
  4153.5 1180.42  4283.8 1170.64  4382.6 1163.01  4481.4 1156.52  4580.2 1150.98
  4787.5 1140.22  4903.5 1132.70  4966.8 1125.31  5000.5 1123.58  5001.0 1123.08
  5006.6 1123.58  5033.5 1129.60  5163.5 1137.12  5376.8 1138.14  5419.4 1141.19
  5490.3 1141.82  5525.5 1140.74  5547.1 1142.02  5553.8 1141.10  5560.9 1142.67
  5584.1 1143.34  5612.9 1144.69  5645.7 1147.02  5653.1 1146.43  5770.0 1151.13
#Mann=11,-1,0
  3921.3    0.05       0  4283.8    0.12       0  4382.6    0.05       0
  4481.4    0.12       0  4580.2    0.05       0  4787.5    0.12       0
  4966.8    0.05       0  5000.5    0.05       0  5006.6    0.05       0
  5584.1    0.12       0  5612.9    0.05       0
Bank Sta=5000.5,5006.6
Exp/Cntr=0.3,0.1

Chan Stop Cuts=-1