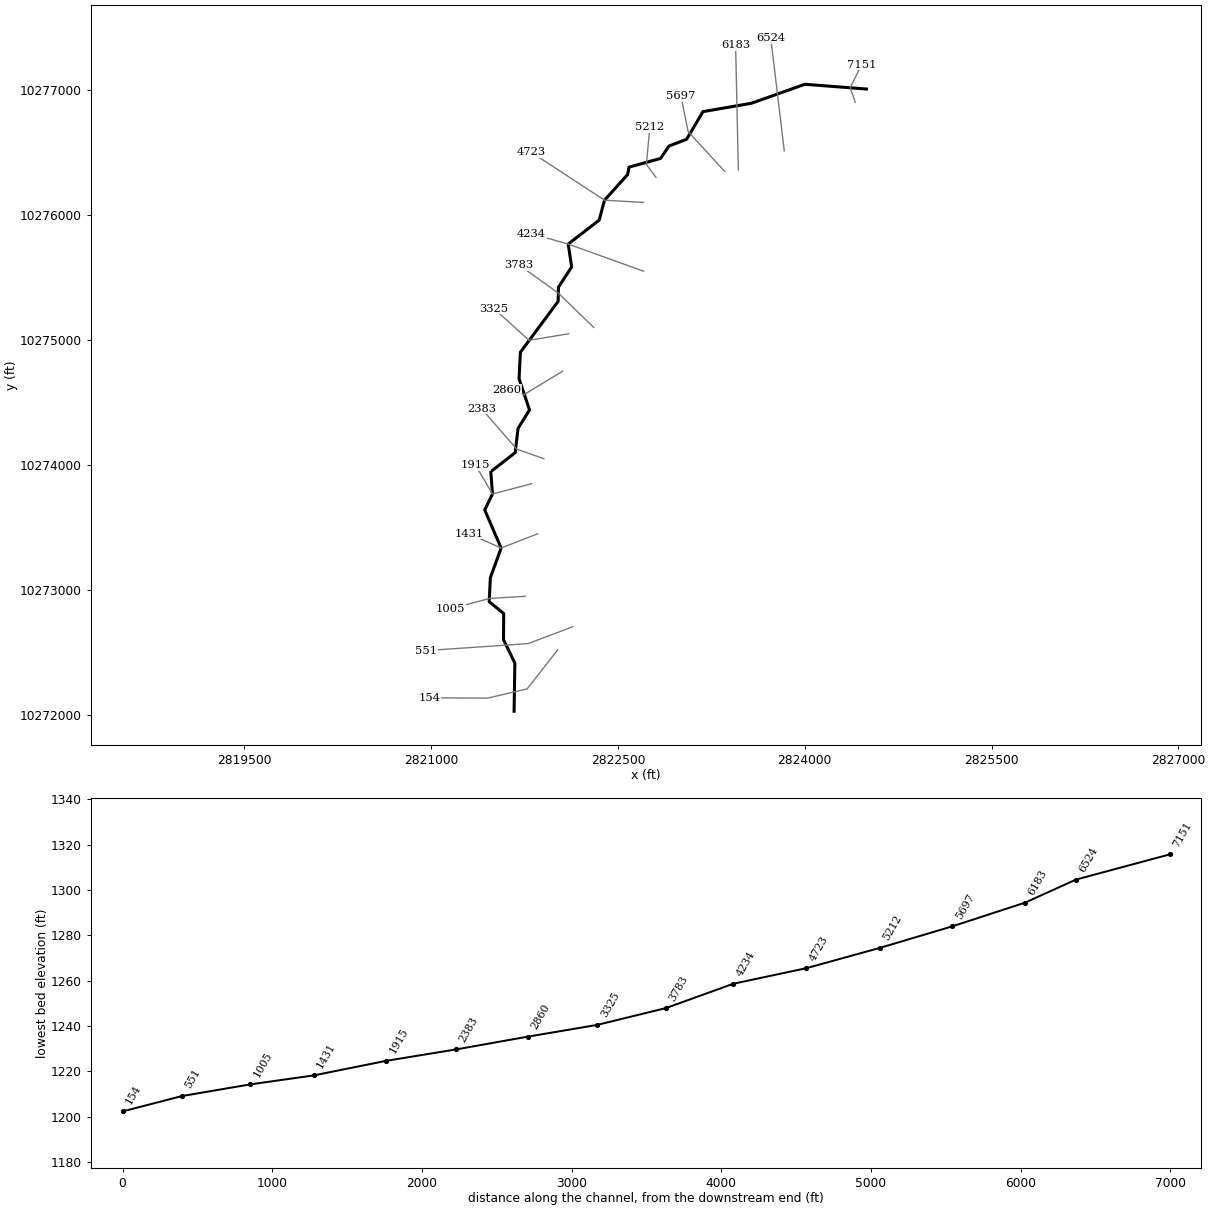
--- LITTLE LLANO 041.prj (project) ---

Proj Title=LITTLE LLANO 041 Base Level Engineering
Current Plan=p01
Default Exp/Contr=0.3,0.1
English Units
Geom File=g01
Flow File=f01
Plan File=p01
Y Axis Title=Elevation
X Axis Title(PF)=Main Channel Distance
X Axis Title(XS)=Station
BEGIN DESCRIPTION:
LITTLE LLANO 041
END DESCRIPTION:
DSS Export Rating Curves= 0
DSS Export Rating Curve Sorted= 0
DSS Export Volume Flow Curves= 0
DXF OffsetX= 0
DXF OffsetY= 0
DXF ScaleX= 1
DXF ScaleY= 10

--- LITTLE LLANO 041.p01 (plan) ---

Plan Title=Multiple Run
Short Identifier=Multiple
Geom File=g01
Flow File=f01
Subcritical Flow
K Sum by GR= 0
Std Step Tol= 0.01
Critical Tol= 0.01
Num of Std Step Trials= 20
Max Error Tol= 0.3
Flow Tol Ratio= 0.001
Split Flow NTrial= 30
Split Flow Tol= 0.02
Split Flow Ratio= 0.02
Log Output Level= 0
Friction Slope Method= 1
Unsteady Friction Slope Method= 2
Unsteady Bridges Friction Slope Method= 1
Parabolic Critical Depth
Global Vel Dist=  1 , 1 , 1
Global Log Level= 0
CheckData=True
Encroach Param= -1, 0, 0, 0
BEGIN DESCRIPTION:
Multiple Run
END DESCRIPTION:

--- LITTLE LLANO 041.f01 (steady flow) ---

Flow Title=Multiple
Number of Profiles=7
Profile Names=10-year,25-year,50-year,1pct_min,100-year,1pct_plu,500-year
River Rch & RM= LITTLE LLANO 041,Reach-1,7151
     291     462     729     559     986    1739    1407
Boundary for River Rch & Prof#=LITTLE LLANO 041,Reach-1,1
Up Type=0
Dn Type=3
Dn Slope=0.005
Boundary for River Rch & Prof#=LITTLE LLANO 041,Reach-1,2
Up Type=0
Dn Type=3
Dn Slope=0.005
Boundary for River Rch & Prof#=LITTLE LLANO 041,Reach-1,3
Up Type=0
Dn Type=3
Dn Slope=0.005
Boundary for River Rch & Prof#=LITTLE LLANO 041,Reach-1,4
Up Type=0
Dn Type=3
Dn Slope=0.005
Boundary for River Rch & Prof#=LITTLE LLANO 041,Reach-1,5
Up Type=0
Dn Type=3
Dn Slope=0.005
Boundary for River Rch & Prof#=LITTLE LLANO 041,Reach-1,6
Up Type=0
Dn Type=3
Dn Slope=0.005
Boundary for River Rch & Prof#=LITTLE LLANO 041,Reach-1,7
Up Type=0
Dn Type=3
Dn Slope=0.005

--- LITTLE LLANO 041.g01 (geometry) ---

Geom Title=Existing Conditions
Program Version=4.10

River Reach=LITTLE LLANO 041,Reach-1
Reach XY= 30
      2824495.25       10277010.       2824001.5       10277048.
      2823571.25       10276896.      2823182.75       10276829.
       2823051.5       10276608.      2822909.75       10276554.
      2822842.75       10276455.      2822588.75       10276385.
        2822578.       10276326.      2822392.25       10276121.
      2822349.75       10275962.      2822100.75       10275770.
      2822128.25       10275587.      2822022.25       10275425.
      2822020.25       10275312.      2821716.75       10274905.
      2821706.25       10274693.      2821789.75       10274444.
      2821697.75       10274295.        2821675.       10274102.
        2821479.       10273950.      2821492.75       10273771.
      2821430.25       10273644.        2821562.       10273339.
       2821475.5       10273101.      2821466.25       10272910.
      2821582.75       10272815.      2821581.25       10272606.
      2821672.25       10272419.      2821666.25       10272034.

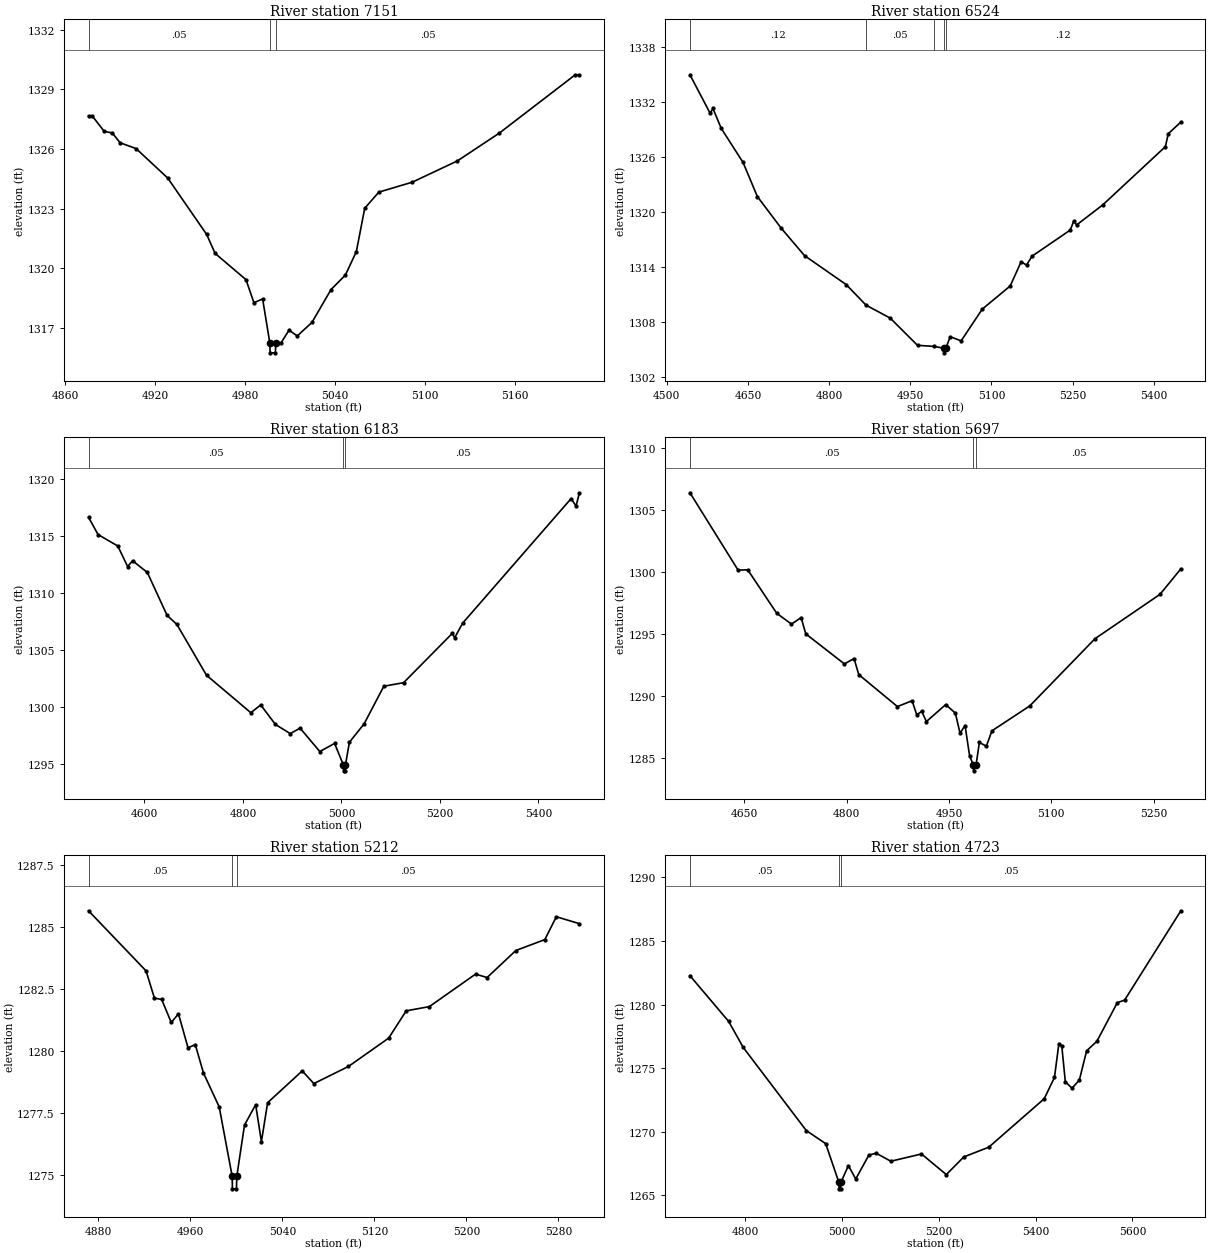
Type RM Length L Ch R = 1 ,7151    ,627,627,627
BEGIN DESCRIPTION:
LITTLE LLANO 041 15.0
END DESCRIPTION:
XS GIS Cut Line= 3
      2824405.69      10276903.1        2824366.       10277021.
      2824455.69     10277203.11
#Sta/Elev= 30
  4875.6 1327.65  4878.2 1327.65  4886.1 1326.88  4891.4 1326.81  4896.7 1326.31
  4907.3 1326.02  4928.4 1324.54  4954.4  1321.7    4960 1320.75  4980.6 1319.43
  4985.9 1318.27  4991.7 1318.46  4996.5 1316.25  4996.7 1315.75  5000.2 1315.75
  5000.5 1316.25    5004 1316.25  5009.3 1316.89  5014.8  1316.6  5024.6 1317.28
  5037.3 1318.93  5046.9 1319.66  5054.2 1320.84  5059.8 1323.02  5069.2 1323.83
  5091.5 1324.33  5121.6  1325.4  5149.6  1326.8  5200.2 1329.73    5203 1329.73
#Mann= 3 ,-1 , 0
  4875.6     .05       0  4996.5     .05       0  5000.5     .05       0
Bank Sta=4996.5,5000.5
XS Rating Curve= 0 ,0
Exp/Cntr=0.3,0.1

Type RM Length L Ch R = 1 ,6524    ,341,341,341
BEGIN DESCRIPTION:
Mapping XS b98c49b0
END DESCRIPTION:
XS GIS Cut Line= 2
      2823835.73     10276515.63      2823727.23     10277416.22
#Sta/Elev= 30
  4542.8 1334.99  4580.2 1330.78  4585.3 1331.31  4600.7 1329.13    4641 1325.41
  4667.4 1321.69  4711.5 1318.23  4754.5 1315.24  4831.6 1312.07  4868.2 1309.83
  4912.9 1308.41  4963.3 1305.44  4994.6 1305.32  5011.7 1305.12  5011.9 1304.62
  5015.7 1305.12  5023.7 1306.38  5043.9 1305.93  5082.9 1309.39  5134.5 1311.92
  5154.7 1314.56  5164.7 1314.21    5175 1315.18  5245.3 1318.02  5252.1 1319.02
  5257.1 1318.58  5305.8 1320.79  5421.3 1327.14  5426.6 1328.55  5449.9 1329.83
#Mann= 5 ,-1 , 0
  4542.8     .12       0  4868.2     .05       0  4994.6     .12       0
  5011.7     .07       0  5015.7     .12       0
Bank Sta=5011.7,5015.7
XS Rating Curve= 0 ,0
Exp/Cntr=0.3,0.1

Type RM Length L Ch R = 1 ,6183    ,486,486,486
BEGIN DESCRIPTION:
Mapping XS 23612444
END DESCRIPTION:
XS GIS Cut Line= 2
      2823466.81     10276363.71      2823445.15     10277360.07
#Sta/Elev= 30
  4486.6 1316.62    4506 1315.11    4546 1314.11    4566 1312.31    4576 1312.82
    4606 1311.79    4646 1308.04    4666 1307.24  4726.1 1302.79  4816.1 1299.51
  4836.1 1300.19  4866.1 1298.48  4896.1 1297.68  4916.1 1298.16  4956.1 1296.11
  4986.1 1296.82  5004.1 1294.92  5004.4 1294.42  5007.9 1294.42  5008.1 1294.92
  5016.1 1296.92  5046.1 1298.54  5086.1 1301.83  5126.2 1302.14  5224.9 1306.45
  5229.9 1306.08  5246.2 1307.36  5466.2 1318.26  5476.2 1317.61  5483.2 1318.77
#Mann= 3 ,-1 , 0
  4486.6     .05       0  5004.1     .03       0  5008.1     .05       0
Bank Sta=5004.1,5008.1
XS Rating Curve= 0 ,0
Exp/Cntr=0.3,0.1

Type RM Length L Ch R = 1 ,5697    ,485,485,485
BEGIN DESCRIPTION:
LITTLE LLANO 041 12.0
END DESCRIPTION:
XS GIS Cut Line= 3
      2823355.71     10276353.08        2823064.       10276669.
      2823005.69     10276953.08
#Sta/Elev= 30
    4570 1306.42  4640.6 1300.18  4654.8  1300.2  4697.3 1296.69  4718.9 1295.82
  4733.1 1296.34  4739.9 1295.03  4796.6  1292.6  4810.7 1293.04  4817.6 1291.74
  4874.3 1289.16  4895.8 1289.63  4902.6  1288.5    4910 1288.77  4916.8 1287.95
  4945.1 1289.32  4959.3 1288.63  4966.1 1287.01  4973.5 1287.63  4980.3 1285.13
  4985.7 1284.47  4985.9 1283.97  4989.7 1284.47  4994.5 1286.26  5004.7 1285.96
  5012.9  1287.2  5068.4 1289.21  5164.1 1294.64  5259.4 1298.22    5290 1300.28
#Mann= 3 ,-1 , 0
    4570     .05       0  4985.7     .03       0  4989.7     .05       0
Bank Sta=4985.7,4989.7
XS Rating Curve= 0 ,0
Exp/Cntr=0.3,0.1

Type RM Length L Ch R = 1 ,5212    ,489,489,489
BEGIN DESCRIPTION:
LITTLE LLANO 041 11.0
END DESCRIPTION:
XS GIS Cut Line= 3
       2822805.7     10276303.09      2822728.75       10276406.
      2822755.68     10276703.08
#Sta/Elev= 30
  4871.5 1285.64  4921.5 1283.22  4928.8 1282.12  4935.1 1282.07  4943.4 1281.14
  4949.7 1281.49    4958 1280.12  4964.3 1280.25  4971.4 1279.11  4985.1 1277.74
  4996.4 1274.94  4996.6 1274.44  5000.1 1274.44  5000.4 1274.94  5007.1 1277.01
  5016.8 1277.83  5021.8 1276.34  5027.2 1277.91  5057.3 1279.19  5067.4 1278.68
  5097.5 1279.37  5132.4 1280.51  5147.7 1281.61  5167.8 1281.78    5208 1283.09
    5218 1282.95    5243 1284.04  5268.2 1284.48  5278.2  1285.4  5298.3 1285.12
#Mann= 3 ,-1 , 0
  4871.5     .05       0  4996.4     .03       0  5000.4     .05       0
Bank Sta=4996.4,5000.4
XS Rating Curve= 0 ,0
Exp/Cntr=0.3,0.1

Type RM Length L Ch R = 1 ,4723    ,489,489,489
BEGIN DESCRIPTION:
LITTLE LLANO 041 10.0
END DESCRIPTION:
XS GIS Cut Line= 3
      2822705.64     10276103.11      2822392.25       10276121.
      2821805.73     10276503.08
#Sta/Elev= 30
  4686.1 1282.27  4766.2 1278.67  4796.2 1276.63  4926.4  1270.1  4966.5 1269.07
  4993.8 1266.02    4994 1265.52  4997.5 1265.52  4997.8 1266.02  5013.4 1267.35
  5028.5 1266.29  5055.6 1268.17  5070.7 1268.32    5101 1267.69  5164.3 1268.26
  5215.6 1266.64  5251.8 1268.03  5303.2 1268.79  5417.8  1272.6  5438.9 1274.27
  5448.1 1276.93  5454.1 1276.73  5461.4 1273.93  5475.1 1273.43  5490.3 1274.06
  5505.4 1276.37  5526.5 1277.11  5568.8 1280.15  5583.8 1280.35    5700 1287.37
#Mann= 3 ,-1 , 0
  4686.1     .05       0  4993.8     .03       0  4997.8     .05       0
Bank Sta=4993.8,4997.8
XS Rating Curve= 0 ,0
Exp/Cntr=0.3,0.1

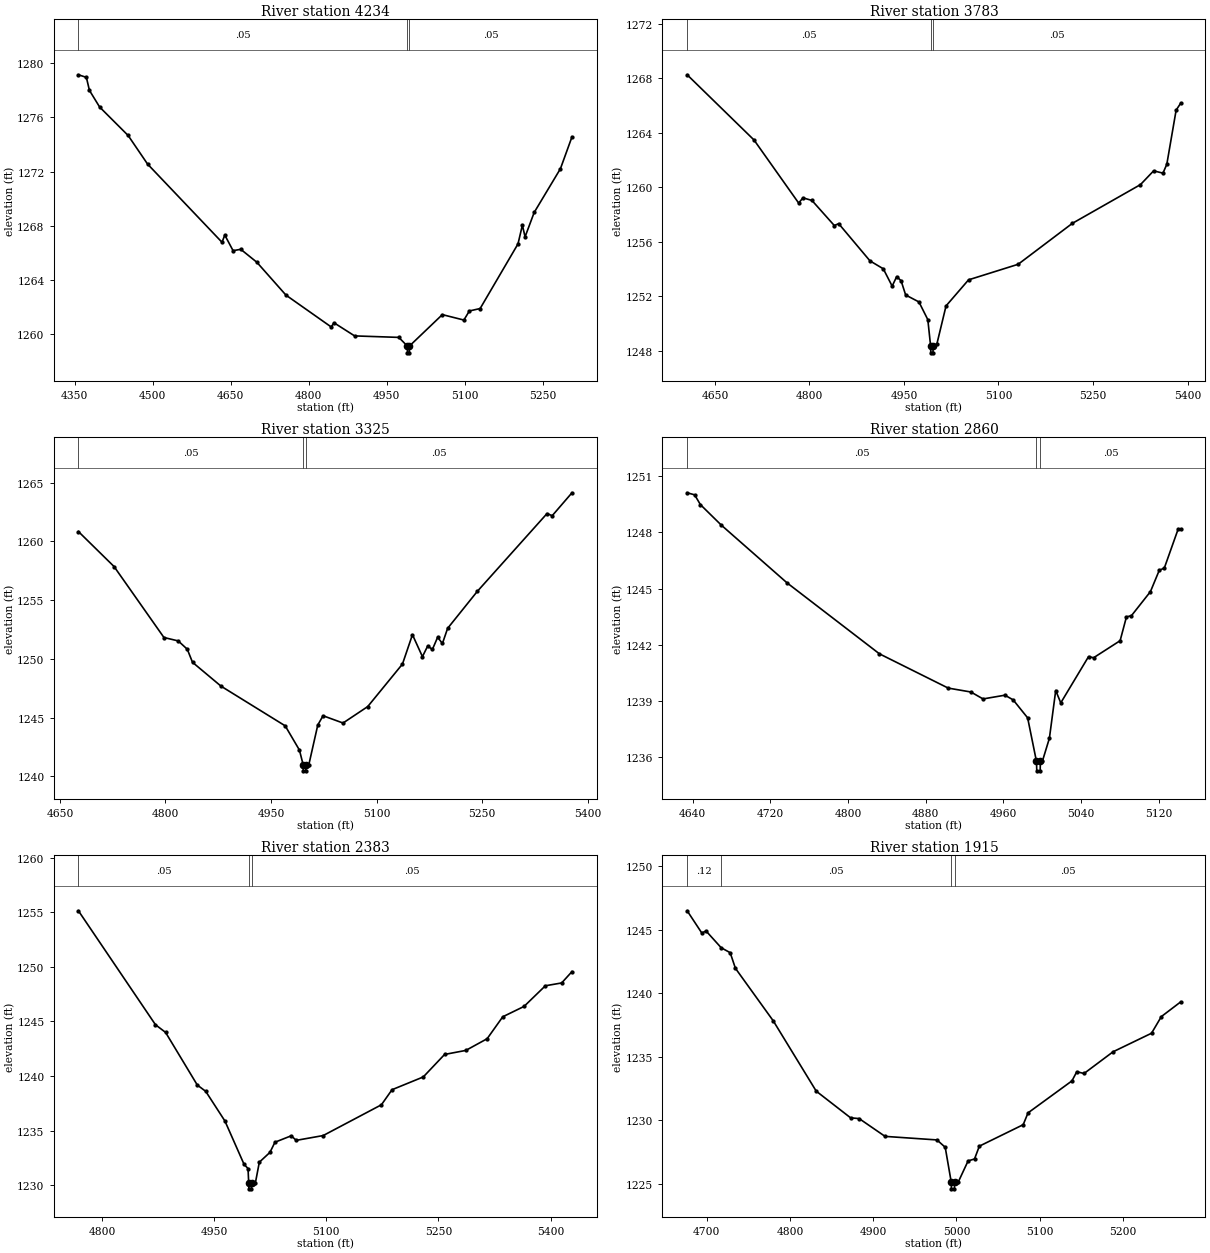
Type RM Length L Ch R = 1 ,4234    ,451,451,451
BEGIN DESCRIPTION:
LITTLE LLANO 041 9.0
END DESCRIPTION:
XS GIS Cut Line= 3
      2822705.65     10275553.13      2822100.75       10275770.
      2821805.73      10275853.1
#Sta/Elev= 30
  4357.4 1279.15  4372.7 1278.96  4378.6    1278  4398.2 1276.77    4453 1274.67
  4490.4 1272.56  4633.5 1266.79  4638.9 1267.32  4654.8 1266.17  4669.6 1266.27
  4700.4 1265.32  4756.5 1262.89  4843.5 1260.54  4848.8 1260.85  4888.5 1259.88
  4973.5 1259.77  4989.9 1259.13  4990.2 1258.63  4993.7 1258.63  4993.9 1259.13
  5057.2 1261.45  5098.6 1261.05  5109.2 1261.72  5129.9  1261.9  5202.7 1266.67
  5211.1 1268.05  5216.3 1267.19  5233.8 1268.99  5284.3 1272.22  5306.5 1274.57
#Mann= 3 ,-1 , 0
  4357.4     .05       0  4989.9     .03       0  4993.9     .05       0
Bank Sta=4989.9,4993.9
XS Rating Curve= 0 ,0
Exp/Cntr=0.3,0.1

Type RM Length L Ch R = 1 ,3783    ,458,458,458
BEGIN DESCRIPTION:
LITTLE LLANO 041 8.0
END DESCRIPTION:
XS GIS Cut Line= 3
      2822305.71     10275103.09       2822022.5       10275377.
      2821705.71      10275603.1
#Sta/Elev= 30
    4606 1268.25  4712.1 1263.47  4782.9 1258.85  4789.8 1259.23    4804 1259.04
  4839.5  1257.2  4846.4 1257.34  4896.1 1254.61  4917.2 1254.03  4931.3 1252.76
  4938.5 1253.46  4945.5 1253.15  4952.7 1252.11  4973.8  1251.6  4987.9  1250.3
  4992.3 1248.37  4992.6 1247.87  4996.1 1247.87  4996.3 1248.37  5002.1 1248.49
  5016.8 1251.31  5052.5 1253.22  5131.2 1254.36  5217.2 1257.36  5325.3  1260.2
  5346.2 1261.21    5361 1261.04  5367.1 1261.69  5381.9 1265.66  5389.2 1266.17
#Mann= 3 ,-1 , 0
    4606     .05       0  4992.3     .03       0  4996.3     .05       0
Bank Sta=4992.3,4996.3
XS Rating Curve= 0 ,0
Exp/Cntr=0.3,0.1

Type RM Length L Ch R = 1 ,3325    ,465,465,465
BEGIN DESCRIPTION:
LITTLE LLANO 041 7.0
END DESCRIPTION:
XS GIS Cut Line= 3
      2822105.66     10275053.11      2821786.25       10275000.
      2821505.66     10275253.13
#Sta/Elev= 30
  4676.2 1260.84  4726.9 1257.86  4797.8 1251.82  4818.1 1251.53    4831 1250.82
  4838.4 1249.71  4878.9 1247.68  4970.2  1244.3  4990.4 1242.24  4995.8 1240.97
    4996 1240.47  4999.5 1240.47  4999.8 1240.97  5003.7 1240.97  5016.5 1244.37
    5024 1245.16  5052.4 1244.54  5087.5 1245.94  5136.9 1249.56  5151.1 1252.06
  5165.3 1250.19  5172.7 1251.09  5179.5 1250.81  5186.9 1251.84  5193.7 1251.31
  5201.1  1252.6  5243.2 1255.74  5342.4 1262.37  5349.8 1262.19  5377.9 1264.14
#Mann= 3 ,-1 , 0
  4676.2     .05       0  4995.8     .03       0  4999.8     .05       0
Bank Sta=4995.8,4999.8
XS Rating Curve= 0 ,0
Exp/Cntr=0.3,0.1

Type RM Length L Ch R = 1 ,2860    ,477,477,477
BEGIN DESCRIPTION:
LITTLE LLANO 041 6.0
END DESCRIPTION:
XS GIS Cut Line= 3
      2822055.65     10274753.09      2821742.75       10274564.
      2821605.72      10274603.1
#Sta/Elev= 30
  4634.4 1250.12  4642.1 1250.01    4648 1249.49  4669.4  1248.4  4737.2 1245.31
  4832.3 1241.52  4903.1 1239.69  4926.5 1239.48    4939 1239.11  4961.5 1239.31
    4970 1239.06  4984.9  1238.1    4994 1235.77  4994.3 1235.27  4997.8 1235.27
    4998 1235.77    5000 1235.77  5007.3 1237.01  5013.8 1239.56    5019  1238.9
  5047.6 1241.37  5052.8 1241.31  5080.1 1242.22  5086.6 1243.49  5091.8 1243.56
  5111.3 1244.84  5120.4 1245.98  5125.6  1246.1  5139.9 1248.19  5142.5 1248.19
#Mann= 3 ,-1 , 0
  4634.4     .05       0    4994     .03       0    4998     .05       0
Bank Sta=4994,4998
XS Rating Curve= 0 ,0
Exp/Cntr=0.3,0.1

Type RM Length L Ch R = 1 ,2383    ,468,468,468
BEGIN DESCRIPTION:
LITTLE LLANO 041 5.0
END DESCRIPTION:
XS GIS Cut Line= 3
      2821905.71      10274053.1      2821687.25       10274130.
      2821405.67     10274453.13
#Sta/Elev= 30
  4768.4 1255.13  4871.5 1244.69    4885 1243.99  4927.4 1239.17  4938.7 1238.59
  4964.4 1235.87    4990  1231.9  4995.3 1231.52  4996.2 1230.16  4996.4 1229.66
  4999.9 1229.66  5000.2 1230.16    5005 1230.16  5010.4  1232.1  5024.6    1233
  5031.3 1233.93  5053.1 1234.52  5059.7  1234.1  5095.8 1234.54  5173.7 1237.36
  5187.9 1238.74  5229.7 1239.91  5258.2 1241.97  5286.6 1242.34  5315.1 1243.41
    5336 1245.42  5364.5 1246.37    5393 1248.26  5414.8 1248.52  5428.6 1249.56
#Mann= 3 ,-1 , 0
  4768.4     .05       0  4996.2     .05       0  5000.2     .05       0
Bank Sta=4996.2,5000.2
XS Rating Curve= 0 ,0
Exp/Cntr=0.3,0.1

Type RM Length L Ch R = 1 ,1915    ,484,484,484
BEGIN DESCRIPTION:
LITTLE LLANO 041 4.0
END DESCRIPTION:
XS GIS Cut Line= 3
      2821805.66      10273853.1      2821492.75       10273771.
      2821355.66     10274003.15
#Sta/Elev= 30
  4676.5  1246.5  4694.1 1244.75  4699.2 1244.91  4717.4 1243.59  4728.2  1243.2
  4734.5 1241.97    4780 1237.83  4831.6  1232.3  4872.9  1230.2  4883.2 1230.14
  4914.3 1228.74  4976.7 1228.46  4986.6 1227.88  4993.9 1225.11  4994.1 1224.61
  4997.6 1224.61  4997.9 1225.11    5002 1225.11  5014.1 1226.81  5021.8 1226.96
  5027.6 1227.97  5080.3 1229.66  5086.1 1230.59  5138.9 1233.11  5144.7 1233.83
  5153.4 1233.69  5188.3  1235.4  5234.5 1236.86  5246.3 1238.17  5269.6 1239.33
#Mann= 4 ,-1 , 0
  4676.5     .12       0  4717.4     .05       0  4993.9     .05       0
  4997.9     .05       0
Bank Sta=4993.9,4997.9
XS Rating Curve= 0 ,0
Exp/Cntr=0.3,0.1

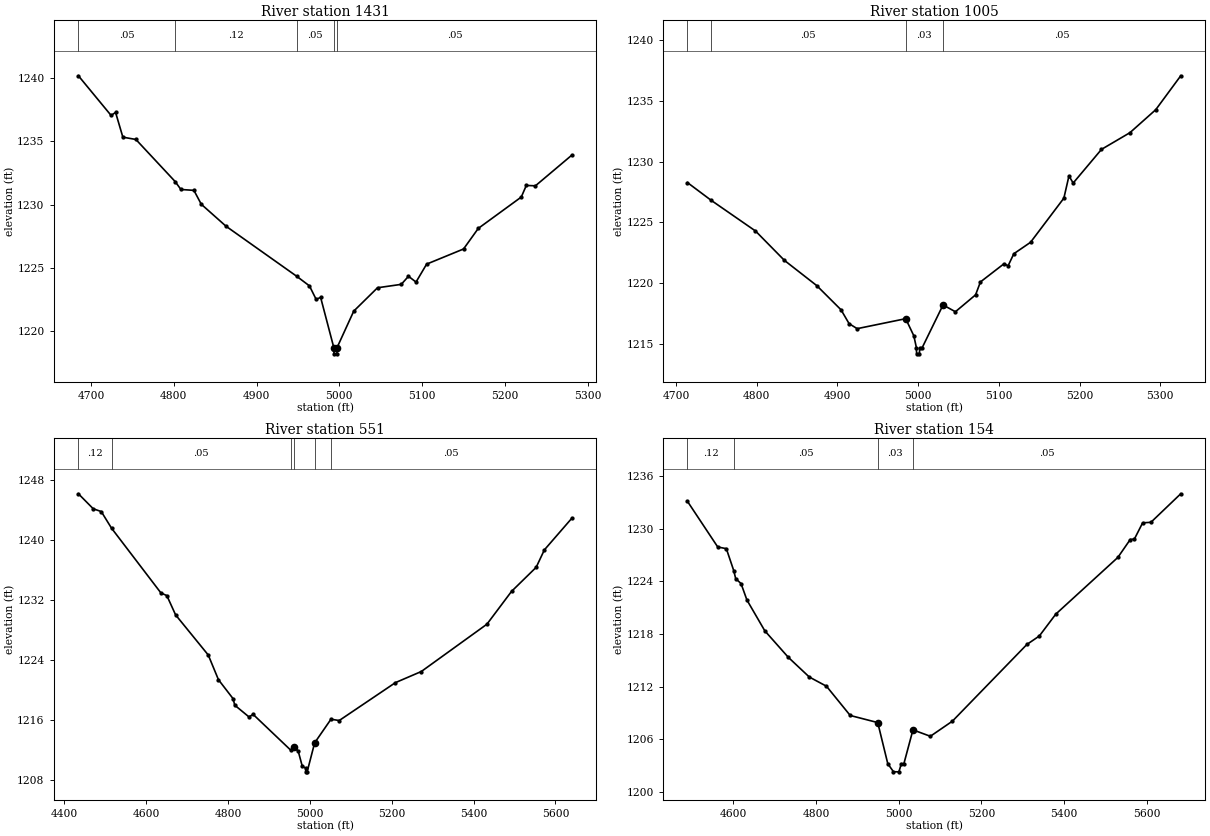
Type RM Length L Ch R = 1 ,1431    ,426,426,426
BEGIN DESCRIPTION:
LITTLE LLANO 041 3.0
END DESCRIPTION:
XS GIS Cut Line= 3
      2821855.71     10273453.12        2821562.       10273339.
      2821305.66     10273453.12
#Sta/Elev= 30
  4684.9 1240.19  4724.4 1237.05  4729.8 1237.29  4738.6 1235.33  4754.3 1235.15
  4801.7 1231.82  4808.7 1231.19  4824.4 1231.12  4833.3 1230.02  4863.2 1228.28
  4948.3 1224.33  4963.9 1223.56    4972 1222.49  4977.4 1222.65  4993.3 1218.68
  4993.6 1218.18  4997.1 1218.18  4997.3 1218.68  5017.4 1221.56  5046.1 1223.41
  5074.8 1223.68  5083.5 1224.32  5092.6 1223.86  5105.4 1225.28    5150 1226.48
  5167.8 1228.11  5219.7 1230.59  5225.8 1231.51  5236.8 1231.48  5280.6  1233.9
#Mann= 5 ,-1 , 0
  4684.9     .05       0  4801.7     .12       0  4948.3     .05       0
  4993.3     .05       0  4997.3     .05       0
Bank Sta=4993.3,4997.3
XS Rating Curve= 0 ,0
Exp/Cntr=0.3,0.1

Type RM Length L Ch R = 1 ,1005    ,454,454,454
BEGIN DESCRIPTION:
LITTLE LLANO 041 2.0
END DESCRIPTION:
XS GIS Cut Line= 3
      2821755.64     10272953.11      2821470.25       10272936.
      2821155.69     10272853.11
#Sta/Elev= 30
  4714.1 1228.28  4743.3 1226.83  4798.4  1224.3  4834.3 1221.88  4874.3 1219.81
  4904.4 1217.82  4914.4 1216.68  4924.4 1216.27  4984.5 1217.09  4994.6 1215.68
  4997.8  1214.7    4998  1214.2  5001.5  1214.2  5001.8  1214.7  5004.9  1214.7
  5030.8 1218.22  5046.1 1217.66  5071.1 1219.05  5077.1 1220.11  5106.2  1221.6
  5111.4 1221.44  5118.5 1222.43  5139.2 1223.37  5180.5    1227  5186.8 1228.83
    5192 1228.24  5227.1 1231.01  5262.3 1232.38  5294.3 1234.27  5325.3 1237.06
#Mann= 4 ,-1 , 0
  4714.1     .12       0  4743.3     .05       0  4984.5     .03       0
  5030.8     .05       0
Bank Sta=4984.5,5030.8
XS Rating Curve= 0 ,0
Exp/Cntr=0.3,0.1

Type RM Length L Ch R = 1 ,551     ,397,397,397
BEGIN DESCRIPTION:
Mapping XS 75cb58a5
END DESCRIPTION:
XS GIS Cut Line= 3
      2822137.99     10272709.63      2821779.91     10272575.08
      2820959.06     10272518.77
#Sta/Elev= 30
  4434.5 1246.13  4470.8 1244.13  4490.4 1243.76  4515.4 1241.55  4636.2 1232.91
  4650.6 1232.56    4672 1229.99  4751.8 1224.64  4776.7 1221.35  4812.3 1218.83
  4816.6 1217.95  4851.3 1216.39  4861.4 1216.73  4952.9 1211.98  4961.6 1212.34
  4971.6 1211.83  4981.6  1209.8  4989.7 1209.57  4989.9 1209.07  4993.4 1209.07
  5011.7 1212.93  5051.6 1216.08  5071.8 1215.91  5209.1 1220.96  5272.3 1222.44
  5432.7 1228.75  5492.8 1233.12    5553 1236.33    5573 1238.65  5639.8 1242.85
#Mann= 6 ,-1 , 0
  4434.5     .12       0  4515.4     .05       0  4952.9     .12       0
  4961.6     .05       0  5011.7     .12       0  5051.6     .05       0
Bank Sta=4961.6,5011.7
XS Rating Curve= 0 ,0
Exp/Cntr=0.3,0.1

Type RM Length L Ch R = 1 ,154     ,0,0,0
BEGIN DESCRIPTION:
LITTLE LLANO 041 1.0
END DESCRIPTION:
XS GIS Cut Line= 4
      2822016.46     10272525.16      2821771.23     10272212.67
      2821454.39     10272138.88      2820983.44     10272141.05
#Sta/Elev= 30
  4488.6  1233.1  4561.9  1227.9  4582.7 1227.71  4600.6 1225.21  4605.3  1224.3
  4618.3 1223.73  4632.5 1221.86  4675.8 1218.35  4732.7 1215.33  4783.4 1213.09
    4825 1212.04  4882.4 1208.71    4949  1207.9 4973.28 1203.22 4987.06  1202.3
 5000.14 1202.29  5006.2 1203.22 5012.28 1203.22  5034.2 1207.07  5076.3 1206.34
  5129.6 1208.06  5309.9  1216.8  5339.9 1217.76  5379.9 1220.26  5529.9 1226.71
  5559.9 1228.75  5569.9  1228.8  5589.9 1230.65  5609.9 1230.71  5682.1 1233.96
#Mann= 4 ,-1 , 0
  4488.6     .12       0  4600.6     .05       0    4949     .03       0
  5034.2     .05       0
Bank Sta=4949,5034.2
XS Rating Curve= 0 ,0
Exp/Cntr=0.3,0.1

Chan Stop Cuts=-1
Use User Specified Reach Order=0
Composite Channel Slope=5