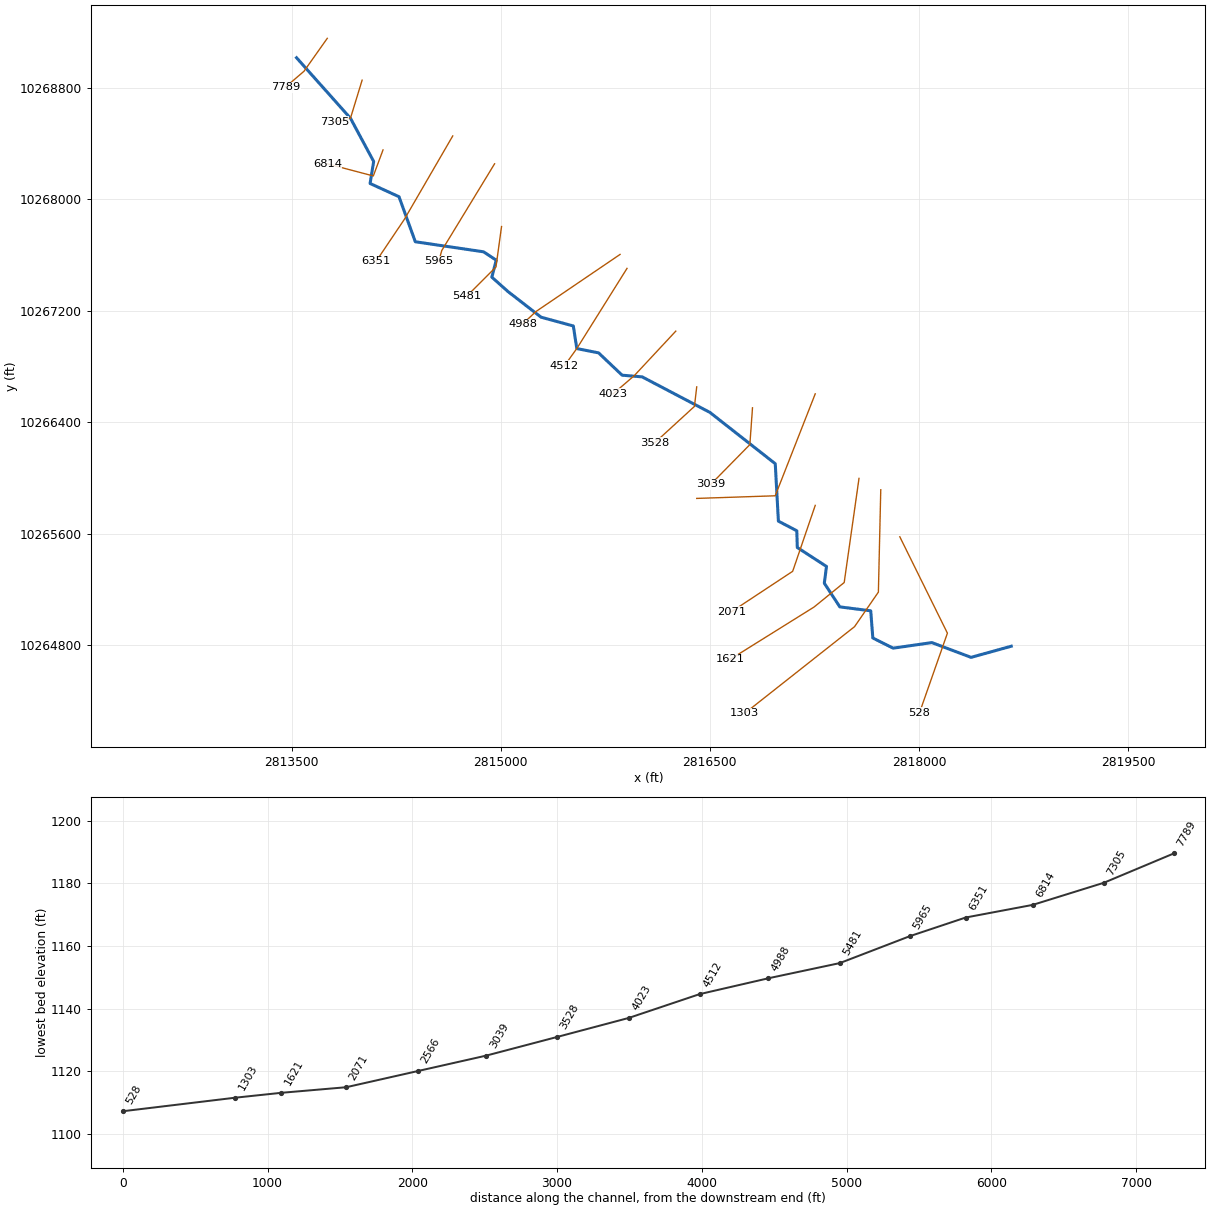
--- LITTLE LLANO 042.prj (project) ---

Proj Title=LITTLE LLANO 042 Base Level Engineering
Current Plan=p01
Default Exp/Contr=0.3,0.1
English Units
Geom File=g01
Flow File=f01
Plan File=p01
BEGIN DESCRIPTION:
LITTLE LLANO 042
END DESCRIPTION:

--- LITTLE LLANO 042.p01 (plan) ---

Plan Title=Multiple Run
Short Identifier=Multiple
Geom File=g01
Flow File=f01
Subcritical Flow
K Sum by GR= 0
Std Step Tol= 0.01
Critical Tol= 0.01
Num of Std Step Trials= 20
Max Error Tol= 0.3
Flow Tol Ratio= 0.001
Split Flow NTrial= 30
Split Flow Tol= 0.02
Split Flow Ratio= 0.02
Log Output Level= 0
Friction Slope Method= 1
Unsteady Friction Slope Method= 2
Unsteady Bridges Friction Slope Method= 1
Parabolic Critical Depth
Global Vel Dist=  1 , 1 , 1
Global Log Level= 0
CheckData=True
Encroach Param= -1, 0, 0, 0
BEGIN DESCRIPTION:
Multiple Run
END DESCRIPTION:

--- LITTLE LLANO 042.f01 (steady flow) ---

Flow Title=Multiple
Number of Profiles=7
Profile Names=10-year,25-year,50-year,1pct_min,100-year,1pct_plu,500-year
River Rch & RM= LITTLE LLANO 042,Reach-1,7789
     435     706    1405    1100    1971    3532    2868
Boundary for River Rch & Prof#=LITTLE LLANO 042,Reach-1,1
Up Type=0
Dn Type=3
Dn Slope=0.005
Boundary for River Rch & Prof#=LITTLE LLANO 042,Reach-1,2
Up Type=0
Dn Type=3
Dn Slope=0.005
Boundary for River Rch & Prof#=LITTLE LLANO 042,Reach-1,3
Up Type=0
Dn Type=3
Dn Slope=0.005
Boundary for River Rch & Prof#=LITTLE LLANO 042,Reach-1,4
Up Type=0
Dn Type=3
Dn Slope=0.005
Boundary for River Rch & Prof#=LITTLE LLANO 042,Reach-1,5
Up Type=0
Dn Type=3
Dn Slope=0.005
Boundary for River Rch & Prof#=LITTLE LLANO 042,Reach-1,6
Up Type=0
Dn Type=3
Dn Slope=0.005
Boundary for River Rch & Prof#=LITTLE LLANO 042,Reach-1,7
Up Type=0
Dn Type=3
Dn Slope=0.005

--- LITTLE LLANO 042.g01 (geometry) ---

Geom Title=Existing Conditions

River Reach=LITTLE LLANO 042,Reach-1
Reach XY= 30
      2813535.25     10269014.00      2813922.00     10268580.00
      2814088.50     10268270.00      2814062.75     10268112.00
      2814270.25     10268017.00      2814387.25     10267694.00
      2814876.75     10267622.00      2814967.50     10267562.00
      2814936.25     10267440.00      2815051.75     10267337.00
      2815289.25     10267153.00      2815520.50     10267090.00
      2815545.50     10266928.00      2815701.75     10266897.00
      2815870.50     10266737.00      2816014.25     10266725.00
      2816500.25     10266470.00      2816969.00     10266102.00
      2816991.50     10265690.00      2817123.50     10265621.00
      2817127.00     10265501.00      2817336.50     10265365.00
      2817320.75     10265245.00      2817432.25     10265075.00
      2817653.75     10265047.00      2817668.75     10264852.00
      2817814.50     10264779.00      2818092.25     10264819.00
      2818373.50     10264713.00      2818661.75     10264793.00

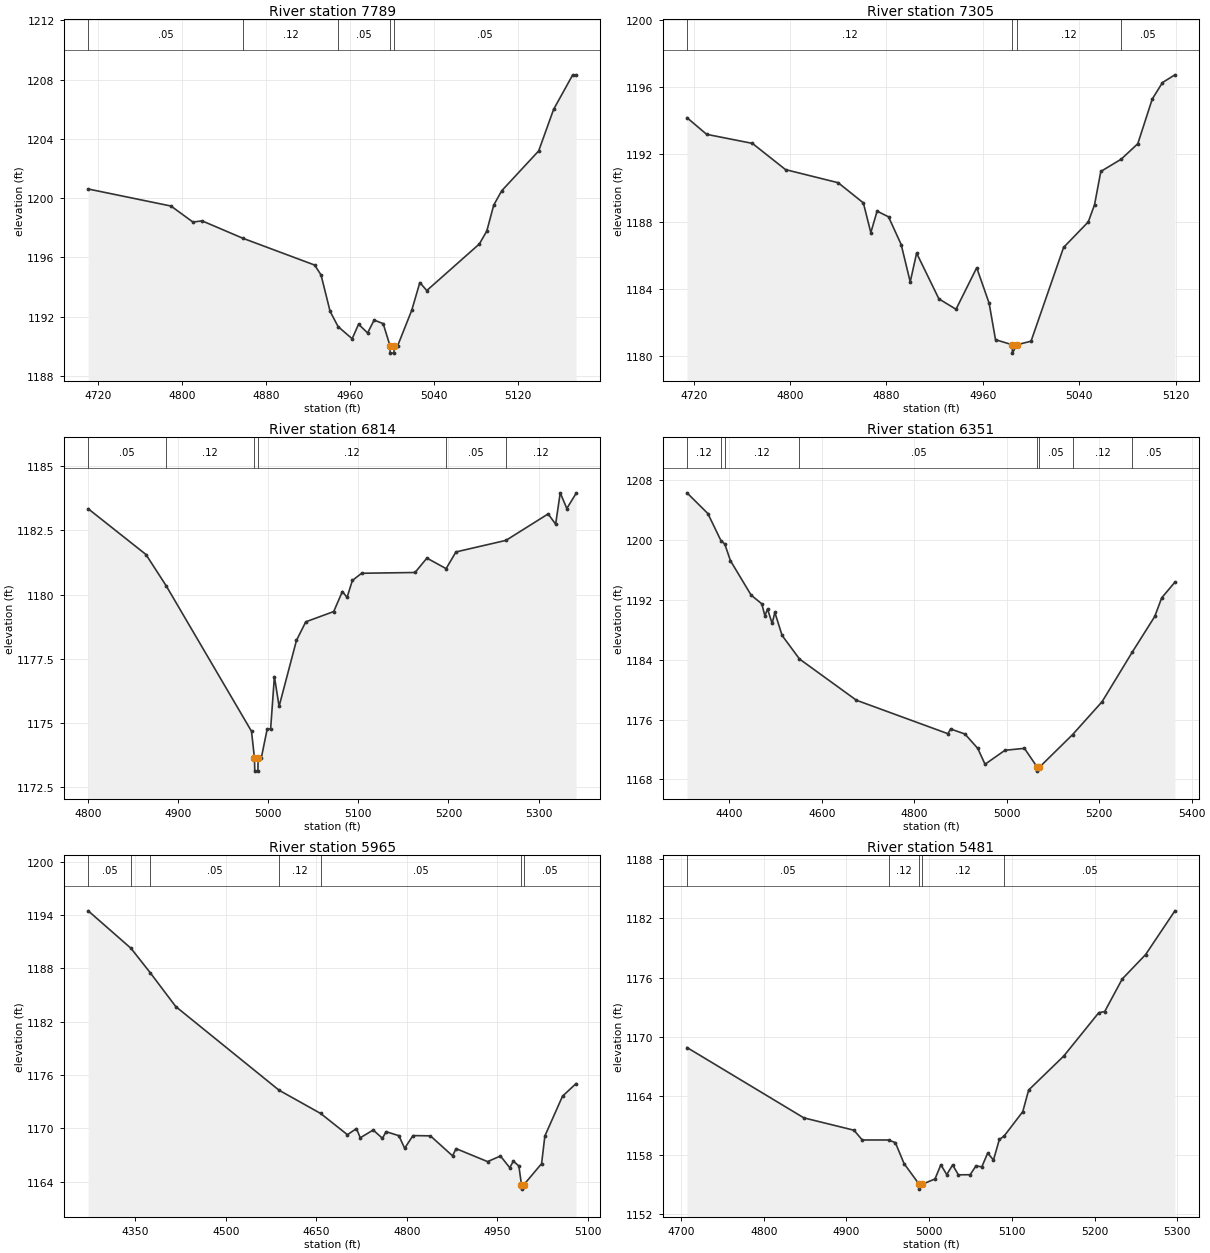
Type RM Length L Ch R = 1,7789,484,484,484
BEGIN DESCRIPTION:
LITTLE LLANO 042 15.0
END DESCRIPTION:
XS GIS Cut Line= 3
      2813755.71     10269153.14      2813588.75     10268917.00
      2813455.72     10268803.14
#Sta/Elev= 30
  4710.8 1200.62  4789.6 1199.47  4810.5 1198.39  4819.2 1198.47  4857.9 1197.30
  4926.3 1195.49  4932.4 1194.82  4941.0 1192.37  4948.6 1191.34  4962.0 1190.52
  4968.1 1191.50  4976.7 1190.91  4982.9 1191.78  4991.5 1191.54  4998.0 1190.05
  4998.2 1189.55  5001.7 1189.55  5002.0 1190.05  5005.3 1190.05  5018.7 1192.44
  5026.4 1194.31  5033.0 1193.77  5083.0 1196.91  5090.1 1197.78  5096.7 1199.53
  5104.3 1200.50  5139.5 1203.19  5153.7 1205.99  5171.9 1208.32  5175.1 1208.32
#Mann=5,-1,0
  4710.8    0.05       0  4857.9    0.12       0  4948.6    0.05       0
  4998.0    0.05       0  5002.0    0.05       0
Bank Sta=4998,5002
Exp/Cntr=0.3,0.1

Type RM Length L Ch R = 1,7305,491,491,491
BEGIN DESCRIPTION:
LITTLE LLANO 042 14.0
END DESCRIPTION:
XS GIS Cut Line= 3
      2814005.67     10268853.07      2813922.00     10268580.00
      2813805.67     10268553.11
#Sta/Elev= 30
  4714.4 1194.19  4730.7 1193.20  4768.7 1192.66  4796.2 1191.10  4839.9 1190.32
  4860.8 1189.12  4867.0 1187.35  4872.2 1188.63  4881.7 1188.29  4892.2 1186.64
  4899.7 1184.42  4905.0 1186.13  4923.5 1183.41  4937.7 1182.79  4954.9 1185.26
  4965.2 1183.15  4970.5 1180.98  4984.3 1180.68  4984.5 1180.18  4988.3 1180.68
  5000.0 1180.89  5027.0 1186.47  5047.5 1187.99  5052.7 1189.01  5057.9 1190.99
  5074.8 1191.72  5088.6 1192.64  5100.6 1195.30  5109.1 1196.28  5119.4 1196.74
#Mann=4,-1,0
  4714.4    0.12       0  4984.3    0.07       0  4988.3    0.12       0
  5074.8    0.05       0
Bank Sta=4984.3,4988.3
Exp/Cntr=0.3,0.1

Type RM Length L Ch R = 1,6814,463,463,463
BEGIN DESCRIPTION:
LITTLE LLANO 042 13.0
END DESCRIPTION:
XS GIS Cut Line= 3
      2814155.70     10268353.14      2814086.00     10268166.00
      2813755.69     10268253.11
#Sta/Elev= 30
  4800.3 1183.34  4864.4 1181.56  4886.7 1180.35  4981.5 1174.68  4984.8 1173.63
  4985.1 1173.13  4988.6 1173.13  4988.8 1173.63  4992.4 1173.65  4998.9 1174.77
  5002.7 1174.77  5006.9 1176.81  5012.1 1175.65  5031.4 1178.22  5041.7 1178.94
  5072.7 1179.34  5082.3 1180.12  5087.5 1179.89  5093.4 1180.55  5103.7 1180.83
  5162.9 1180.86  5176.1 1181.42  5197.4 1181.01  5208.3 1181.66  5263.8 1182.11
  5310.6 1183.14  5318.9 1182.74  5324.0 1183.96  5331.3 1183.35  5341.6 1183.94
#Mann=6,-1,0
  4800.3    0.05       0  4886.7    0.12       0  4984.8    0.07       0
  4988.8    0.12       0  5197.4    0.05       0  5263.8    0.12       0
Bank Sta=4984.8,4988.8
Exp/Cntr=0.3,0.1

Type RM Length L Ch R = 1,6351,386,386,386
BEGIN DESCRIPTION:
LITTLE LLANO 042 12.0
END DESCRIPTION:
XS GIS Cut Line= 3
      2814655.66     10268453.07      2814308.75     10267855.00
      2814105.70     10267553.14
#Sta/Elev= 30
  4308.6 1206.35  4353.7 1203.58  4382.0 1199.96  4390.3 1199.50  4402.5 1197.28
  4447.3 1192.66  4470.4 1191.49  4477.1 1189.89  4482.8 1190.80  4492.8 1188.86
  4498.6 1190.35  4514.3 1187.26  4551.9 1184.11  4675.0 1178.59  4872.9 1174.11
  4878.7 1174.74  4909.7 1174.07  4937.5 1172.14  4953.2 1170.02  4996.3 1171.89
  5038.4 1172.15  5066.4 1169.60  5066.6 1169.10  5070.4 1169.60  5142.7 1174.00
  5206.3 1178.39  5271.5 1185.02  5320.3 1189.81  5335.3 1192.30  5363.8 1194.39
#Mann=8,-1,0
  4308.6    0.12       0  4382.0    0.05       0  4390.3    0.12       0
  4551.9    0.05       0  5066.4    0.05       0  5070.4    0.05       0
  5142.7    0.12       0  5271.5    0.05       0
Bank Sta=5066.4,5070.4
Exp/Cntr=0.3,0.1

Type RM Length L Ch R = 1,5965,484,484,484
BEGIN DESCRIPTION:
LITTLE LLANO 042 11.0
END DESCRIPTION:
XS GIS Cut Line= 3
      2814955.67     10268253.08      2814576.75     10267631.00
      2814555.68     10267553.10
#Sta/Elev= 30
  4271.6 1194.49  4342.6 1190.27  4374.7 1187.50  4416.8 1183.71  4588.1 1174.29
  4657.1 1171.67  4701.5 1169.28  4716.5 1169.97  4722.8 1168.93  4744.2 1169.81
  4759.6 1168.87  4765.5 1169.62  4786.8 1169.17  4796.4 1167.75  4810.2 1169.18
  4839.1 1169.15  4875.8 1166.90  4881.7 1167.71  4933.9 1166.25  4955.3 1166.88
  4970.7 1165.56  4976.6 1166.30  4985.8 1165.76  4990.1 1163.65  4990.3 1163.15
  4994.1 1163.65  5023.5 1166.02  5028.9 1169.13  5058.2 1173.62  5080.7 1175.04
#Mann=7,-1,0
  4271.6    0.05       0  4342.6    0.12       0  4374.7    0.05       0
  4588.1    0.12       0  4657.1    0.05       0  4990.1    0.05       0
  4994.1    0.05       0
Bank Sta=4990.1,4994.1
Exp/Cntr=0.3,0.1

Type RM Length L Ch R = 1,5481,493,493,493
BEGIN DESCRIPTION:
LITTLE LLANO 042 10.0
END DESCRIPTION:
XS GIS Cut Line= 3
      2815005.68     10267803.06      2814965.75     10267513.00
      2814755.65     10267303.08
#Sta/Elev= 30
  4707.2 1168.91  4848.5 1161.78  4909.0 1160.53  4919.1 1159.54  4950.8 1159.54
  4959.1 1159.27  4969.6 1157.15  4987.8 1155.06  4988.0 1154.56  4991.8 1155.06
  5007.0 1155.59  5014.1 1157.03  5021.2 1156.03  5028.3 1157.01  5035.3 1156.01
  5049.5 1156.02  5056.5 1156.91  5063.6 1156.82  5070.7 1158.21  5077.7 1157.51
  5084.8 1159.60  5090.4 1159.92  5113.1 1162.41  5120.2 1164.60  5162.6 1168.04
  5205.0 1172.44  5212.1 1172.55  5233.3 1175.85  5261.6 1178.33  5297.0 1182.76
#Mann=5,-1,0
  4707.2    0.05       0  4950.8    0.12       0  4987.8    0.07       0
  4991.8    0.12       0  5090.4    0.05       0
Bank Sta=4987.8,4991.8
Exp/Cntr=0.3,0.1

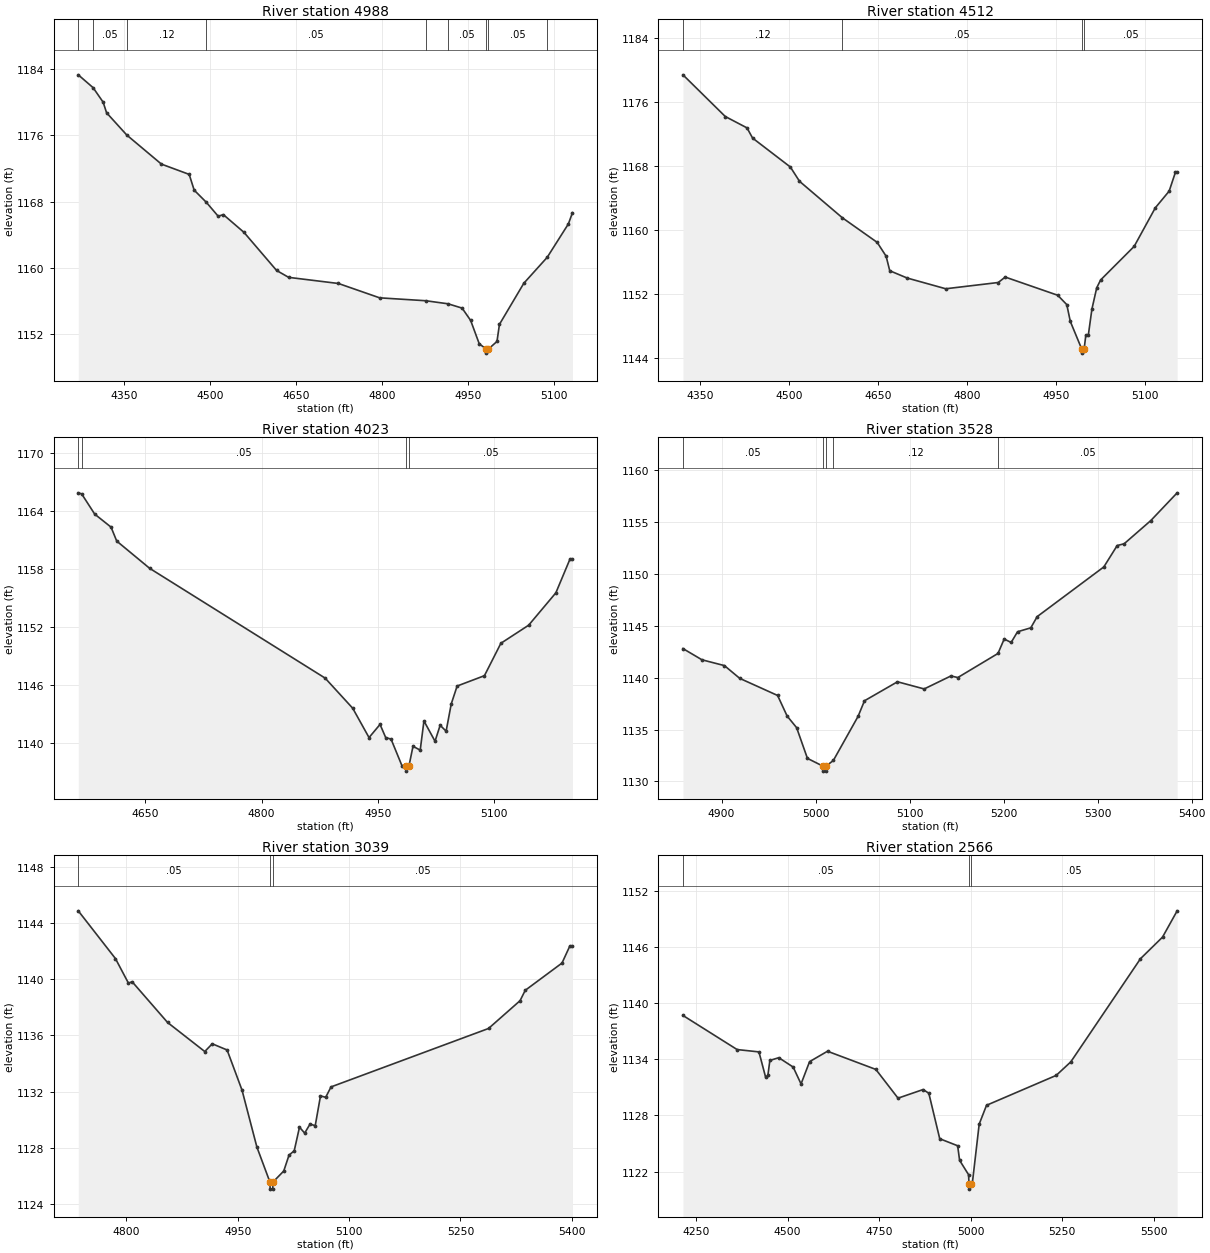
Type RM Length L Ch R = 1,4988,476,476,476
BEGIN DESCRIPTION:
LITTLE LLANO 042 9.0
END DESCRIPTION:
XS GIS Cut Line= 3
      2815855.67     10267603.10      2815251.75     10267193.00
      2815155.66     10267103.09
#Sta/Elev= 30
  4270.0 1183.29  4295.9 1181.74  4313.4 1179.99  4319.4 1178.71  4354.7 1176.02
  4415.0 1172.52  4463.4 1171.28  4472.1 1169.38  4493.2 1167.92  4514.0 1166.23
  4522.9 1166.43  4558.9 1164.29  4615.8 1159.69  4636.8 1158.86  4723.6 1158.12
  4795.4 1156.39  4875.8 1156.04  4914.7 1155.67  4939.2 1155.15  4954.1 1153.66
  4969.1 1150.84  4981.2 1150.22  4981.4 1149.72  4985.2 1150.22  5000.0 1151.13
  5004.3 1153.19  5046.8 1158.15  5087.6 1161.28  5124.5 1165.31  5131.6 1166.66
#Mann=9,-1,0
  4270.0    0.12       0  4295.9    0.05       0  4354.7    0.12       0
  4493.2    0.05       0  4875.8    0.12       0  4914.7    0.05       0
  4981.2    0.05       0  4985.2    0.05       0  5087.6    0.12       0
Bank Sta=4981.2,4985.2
Exp/Cntr=0.3,0.1

Type RM Length L Ch R = 1,4512,489,489,489
BEGIN DESCRIPTION:
LITTLE LLANO 042 8.0
END DESCRIPTION:
XS GIS Cut Line= 3
      2815905.69     10267503.12      2815545.50     10266928.00
      2815455.70     10266803.14
#Sta/Elev= 30
  4321.4 1179.37  4392.7 1174.17  4429.3 1172.75  4438.7 1171.48  4502.3 1167.87
  4517.7 1166.09  4589.8 1161.54  4648.5 1158.47  4663.6 1156.74  4669.7 1154.93
  4699.0 1154.02  4764.0 1152.68  4852.4 1153.46  4864.2 1154.14  4952.6 1151.87
  4967.9 1150.70  4973.8 1148.61  4993.1 1145.15  4993.3 1144.65  4997.1 1145.15
  4999.9 1146.86  5004.1 1146.86  5010.2 1150.14  5018.3 1152.80  5024.9 1153.78
  5081.4 1157.97  5117.0 1162.78  5140.3 1164.86  5150.8 1167.20  5153.8 1167.20
#Mann=4,-1,0
  4321.4    0.12       0  4589.8    0.05       0  4993.1    0.05       0
  4997.1    0.05       0
Bank Sta=4993.1,4997.1
Exp/Cntr=0.3,0.1

Type RM Length L Ch R = 1,4023,495,495,495
BEGIN DESCRIPTION:
LITTLE LLANO 042 7.0
END DESCRIPTION:
XS GIS Cut Line= 3
      2816255.68     10267053.11      2815958.00     10266734.00
      2815805.71     10266603.13
#Sta/Elev= 30
  4563.6 1165.84  4568.0 1165.73  4584.8 1163.64  4605.9 1162.29  4613.2 1160.85
  4655.7 1158.03  4881.9 1146.68  4917.5 1143.56  4938.5 1140.53  4952.7 1141.89
  4960.0 1140.53  4966.9 1140.37  4981.1 1137.59  4985.9 1137.56  4986.1 1137.06
  4989.9 1137.56  4995.2 1139.63  5004.5 1139.23  5009.3 1142.25  5023.6 1140.15
  5030.2 1141.80  5037.9 1141.19  5044.5 1144.01  5052.1 1145.86  5087.3 1146.93
  5108.5 1150.28  5144.3 1152.15  5179.4 1155.50  5197.5 1158.97  5200.8 1158.97
#Mann=4,-1,0
  4563.6    0.12       0  4568.0    0.05       0  4985.9    0.05       0
  4989.9    0.05       0
Bank Sta=4985.9,4989.9
Exp/Cntr=0.3,0.1

Type RM Length L Ch R = 1,3528,489,489,489
BEGIN DESCRIPTION:
LITTLE LLANO 042 6.0
END DESCRIPTION:
XS GIS Cut Line= 3
      2816405.69     10266653.14      2816389.25     10266513.00
      2816105.72     10266253.14
#Sta/Elev= 30
  4858.9 1142.80  4879.1 1141.72  4903.0 1141.16  4919.3 1139.93  4959.6 1138.28
  4969.7 1136.30  4979.8 1135.18  4991.3 1132.22  5007.4 1131.49  5007.7 1130.99
  5011.2 1130.99  5011.4 1131.49  5018.9 1132.02  5045.2 1136.27  5052.0 1137.77
  5087.1 1139.60  5115.5 1138.91  5143.9 1140.16  5151.3 1140.01  5194.0 1142.33
  5200.6 1143.72  5208.0 1143.39  5214.8 1144.42  5228.9 1144.80  5235.7 1145.88
  5306.6 1150.67  5320.8 1152.73  5328.2 1152.90  5356.6 1155.14  5384.6 1157.81
#Mann=5,-1,0
  4858.9    0.05       0  5007.4    0.03       0  5011.4    0.05       0
  5018.9    0.12       0  5194.0    0.05       0
Bank Sta=5007.4,5011.4
Exp/Cntr=0.3,0.1

Type RM Length L Ch R = 1,3039,473,473,473
BEGIN DESCRIPTION:
LITTLE LLANO 042 5.0
END DESCRIPTION:
XS GIS Cut Line= 3
      2816805.68     10266503.12      2816786.75     10266239.00
      2816505.69     10265953.12
#Sta/Elev= 30
  4735.2 1144.87  4785.3 1141.47  4802.8 1139.72  4807.8 1139.82  4855.5 1136.92
  4905.6 1134.85  4915.7 1135.40  4935.7 1134.96  4955.8 1132.10  4975.8 1128.05
  4993.4 1125.55  4993.7 1125.05  4997.2 1125.05  4997.4 1125.55  5012.0 1126.34
  5019.1 1127.47  5026.1 1127.78  5033.2 1129.46  5040.2 1129.04  5047.4 1129.68
  5054.4 1129.57  5061.5 1131.69  5068.5 1131.59  5075.7 1132.33  5287.8 1136.49
  5330.3 1138.47  5337.3 1139.21  5386.8 1141.15  5397.4 1142.37  5400.9 1142.37
#Mann=3,-1,0
  4735.2    0.05       0  4993.4    0.05       0  4997.4    0.05       0
Bank Sta=4993.4,4997.4
Exp/Cntr=0.3,0.1

Type RM Length L Ch R = 1,2566,495,495,495
BEGIN DESCRIPTION:
LITTLE LLANO 042 4.0
END DESCRIPTION:
XS GIS Cut Line= 3
      2817255.68     10266603.11      2816968.75     10265872.00
      2816405.67     10265853.11
#Sta/Elev= 30
  4214.6 1138.66  4362.4 1135.02  4422.0 1134.77  4440.2 1132.07  4446.4 1132.26
  4451.8 1133.86  4476.2 1134.15  4515.4 1133.15  4536.9 1131.35  4560.2 1133.73
  4609.1 1134.84  4741.0 1132.90  4801.6 1129.83  4869.9 1130.75  4885.6 1130.36
  4915.4 1125.50  4964.3 1124.75  4969.6 1123.20  4994.1 1121.66  4995.4 1120.62
  4995.6 1120.12  4999.4 1120.62  5004.0 1120.62  5023.1 1127.06  5043.1 1129.07
  5233.2 1132.26  5273.2 1133.71  5463.3 1144.72  5523.4 1147.02  5563.4 1149.83
#Mann=3,-1,0
  4214.6    0.05       0  4995.4    0.05       0  4999.4    0.05       0
Bank Sta=4995.4,4999.4
Exp/Cntr=0.3,0.1

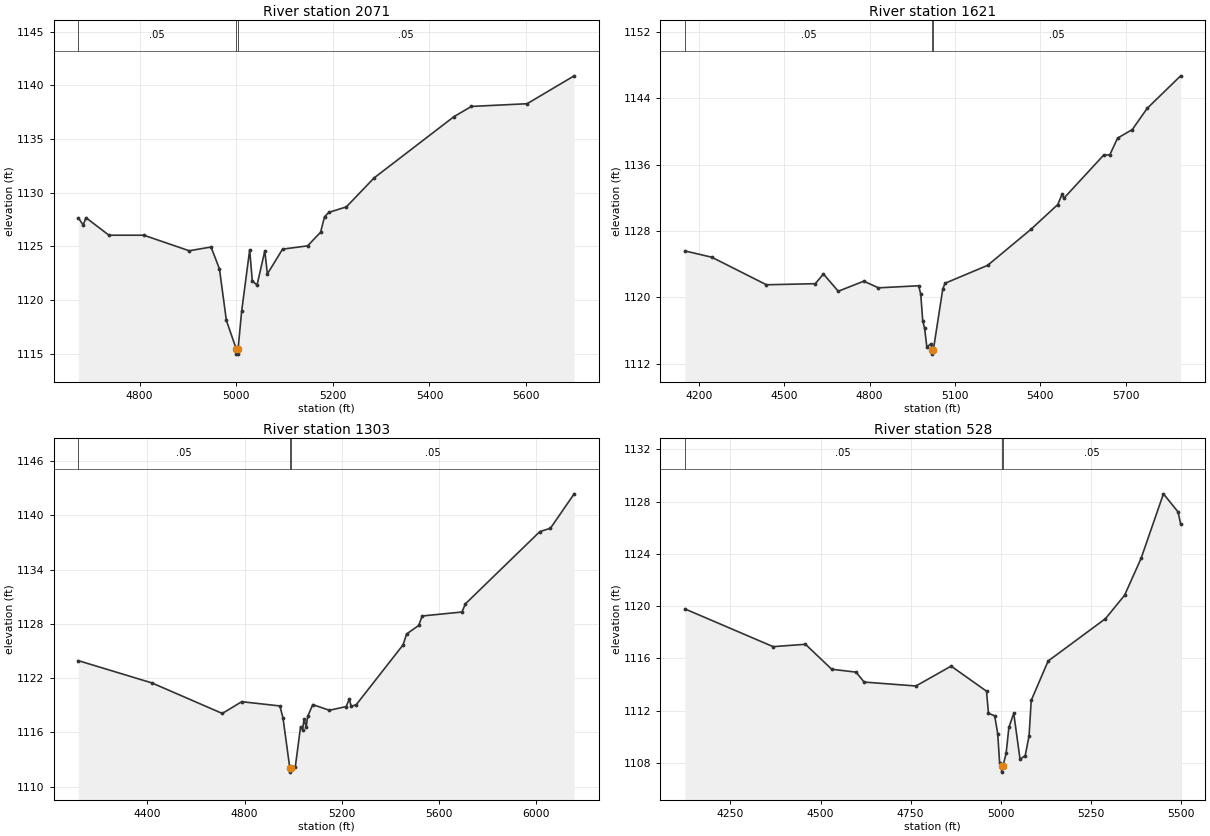
Type RM Length L Ch R = 1,2071,450,450,450
BEGIN DESCRIPTION:
LITTLE LLANO 042 3.0
END DESCRIPTION:
XS GIS Cut Line= 3
      2817255.67     10265803.07      2817094.05     10265330.44
      2816654.42     10265040.19
#Sta/Elev= 30
  4673.2 1127.65  4683.5 1126.98  4688.8 1127.68  4736.6 1126.04  4808.7 1126.04
  4902.7 1124.59  4947.9 1124.94  4965.3 1122.90  4979.6 1118.11  4999.9 1115.46
  5000.1 1114.96  5003.6 1114.96  5003.9 1115.46  5011.3 1118.98  5027.9 1124.68
  5033.2 1121.81  5043.0 1121.38  5059.2 1124.58  5064.5 1122.43  5095.9 1124.74
  5147.8 1125.05  5174.7 1126.32  5182.8 1127.76  5191.9 1128.17  5228.0 1128.68
  5285.2 1131.37  5450.8 1137.09  5486.9 1138.04  5602.1 1138.29  5699.5 1140.89
#Mann=3,-1,0
  4673.2    0.05       0  4999.9    0.05       0  5003.9    0.05       0
Bank Sta=4999.9,5003.9
Exp/Cntr=0.3,0.1

Type RM Length L Ch R = 1,1621,318,318,318
BEGIN DESCRIPTION:
LITTLE LLANO 042 2.0
END DESCRIPTION:
XS GIS Cut Line= 4
      2817569.70     10265996.98      2817463.52     10265249.90
      2817247.70     10265074.35      2816645.89     10264698.75
#Sta/Elev= 30
  4150.8 1125.61  4245.6 1124.85  4437.5 1121.53  4609.2 1121.66  4637.9 1122.83
  4690.0 1120.75  4779.7 1121.96  4831.4 1121.16  4972.6 1121.41  4979.9 1120.38
  4986.9 1117.16  4993.4 1116.31  5001.3 1114.02  5015.7 1114.42  5020.1 1113.67
  5020.4 1113.17  5024.1 1113.67  5057.3 1121.02  5065.2 1121.71  5214.9 1123.87
  5367.0 1128.21  5461.4 1131.20  5476.7 1132.46  5482.6 1131.95  5622.1 1137.14
  5644.2 1137.19  5671.4 1139.20  5723.3 1140.24  5775.2 1142.78  5893.0 1146.71
#Mann=3,-1,0
  4150.8    0.05       0  5020.1    0.03       0  5024.1    0.05       0
Bank Sta=5020.1,5024.1
Exp/Cntr=0.3,0.1

Type RM Length L Ch R = 1,1303,775,775,775
BEGIN DESCRIPTION:
Mapping XS b8b79365
END DESCRIPTION:
XS GIS Cut Line= 4
      2817725.74     10265915.16      2817708.67     10265181.05
      2817537.94     10264933.50      2816749.52     10264311.28
#Sta/Elev= 30
  4115.8 1123.94  4417.9 1121.48  4708.0 1118.10  4788.0 1119.40  4944.8 1118.93
  4957.6 1117.61  4985.4 1112.11  4985.6 1111.61  4989.4 1112.11  5008.3 1112.20
  5029.8 1116.62  5038.1 1116.30  5044.2 1117.48  5053.0 1116.60  5059.1 1117.77
  5080.0 1119.08  5148.4 1118.45  5217.4 1118.86  5230.3 1119.68  5238.4 1118.88
  5259.2 1119.08  5451.6 1125.69  5466.0 1126.89  5515.7 1127.83  5530.1 1128.88
  5693.7 1129.32  5708.1 1130.23  6014.3 1138.22  6057.6 1138.58  6155.2 1142.39
#Mann=3,-1,0
  4115.8    0.05       0  4985.4    0.03       0  4989.4    0.05       0
Bank Sta=4985.4,4989.4
Exp/Cntr=0.3,0.1

Type RM Length L Ch R = 1,528,0,0,0
BEGIN DESCRIPTION:
LITTLE LLANO 042 1.0
END DESCRIPTION:
XS GIS Cut Line= 3
      2817862.33     10265577.97      2818203.78     10264886.55
      2818003.78     10264316.34
#Sta/Elev= 30
  4123.4 1119.79  4368.4 1116.90  4458.1 1117.08  4531.0 1115.17  4598.4 1114.95
  4620.8 1114.19  4764.5 1113.89  4862.2 1115.41  4960.4 1113.49  4965.7 1111.80
  4983.0 1111.61  4991.4 1110.25  4996.7 1108.02  5002.2 1107.80  5002.4 1107.30
  5006.2 1107.80  5014.7 1108.73  5022.4 1110.72  5035.9 1111.80  5053.4 1108.28
  5067.7 1108.57  5078.3 1110.06  5084.4 1112.79  5131.3 1115.80  5290.3 1119.04
  5343.3 1120.83  5389.1 1123.65  5451.1 1128.59  5491.6 1127.21  5498.8 1126.30
#Mann=3,-1,0
  4123.4    0.05       0  5002.2    0.05       0  5006.2    0.05       0
Bank Sta=5002.2,5006.2
Exp/Cntr=0.3,0.1

Chan Stop Cuts=-1