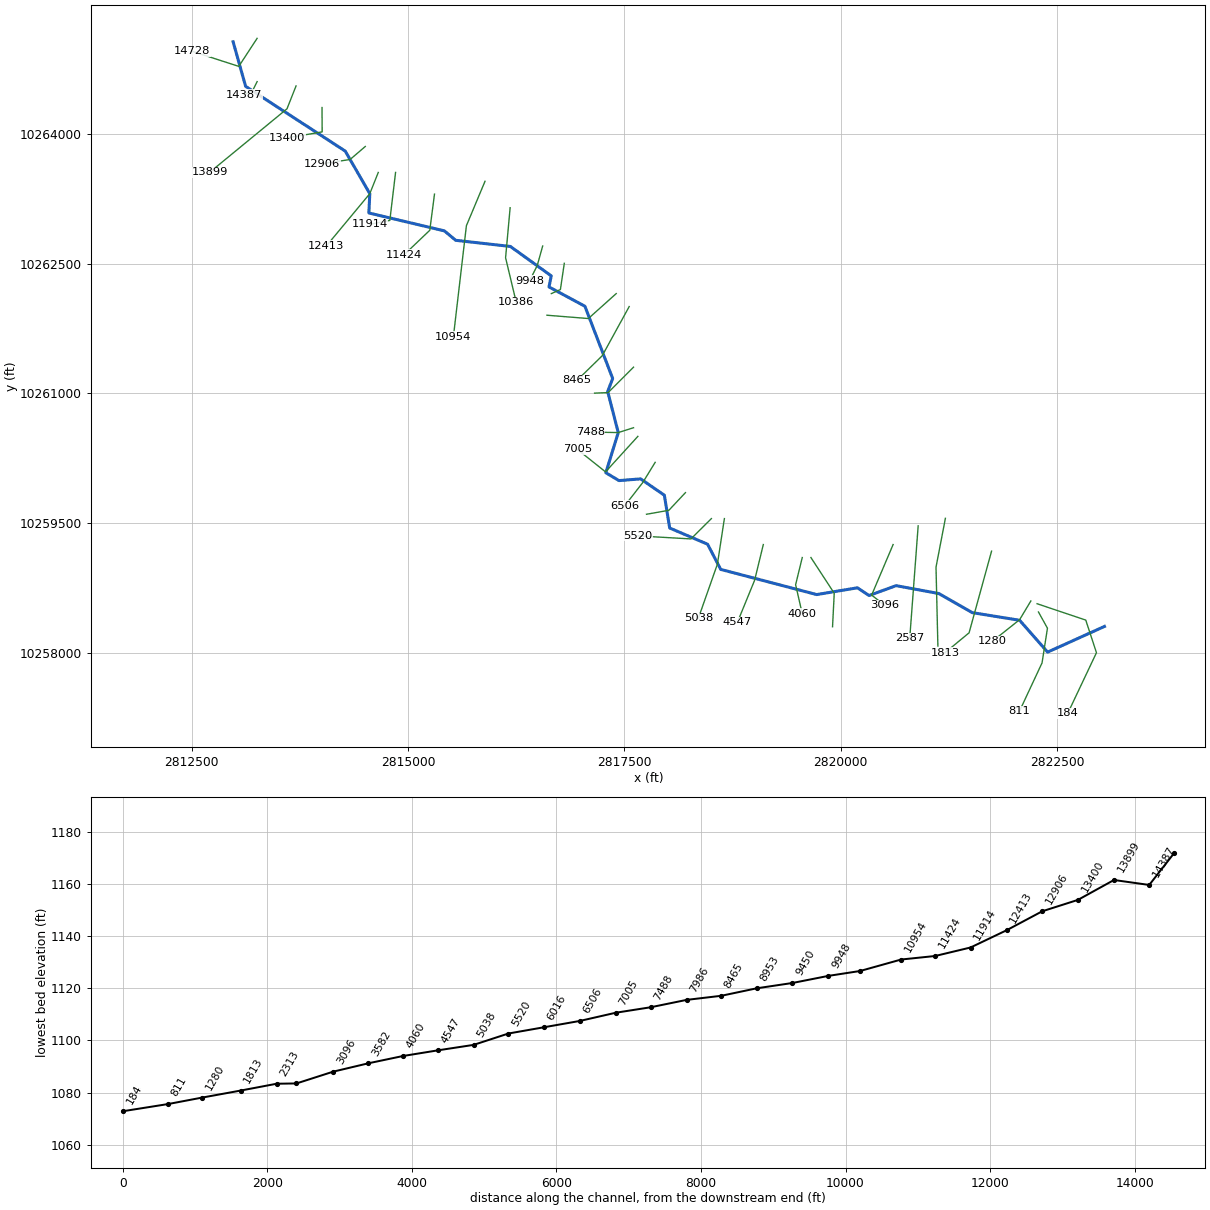
--- LITTLE LLANO 043.prj (project) ---

Proj Title=LITTLE LLANO 043 Base Level Engineering
Current Plan=p01
Default Exp/Contr=0.3,0.1
English Units
Geom File=g01
Flow File=f01
Plan File=p01
BEGIN DESCRIPTION:
LITTLE LLANO 043
END DESCRIPTION:

--- LITTLE LLANO 043.p01 (plan) ---

Plan Title=Multiple Run
Short Identifier=Multiple
Geom File=g01
Flow File=f01
Subcritical Flow
K Sum by GR= 0
Std Step Tol= 0.01
Critical Tol= 0.01
Num of Std Step Trials= 20
Max Error Tol= 0.3
Flow Tol Ratio= 0.001
Split Flow NTrial= 30
Split Flow Tol= 0.02
Split Flow Ratio= 0.02
Log Output Level= 0
Friction Slope Method= 1
Unsteady Friction Slope Method= 2
Unsteady Bridges Friction Slope Method= 1
Parabolic Critical Depth
Global Vel Dist=  1 , 1 , 1
Global Log Level= 0
CheckData=True
Encroach Param= -1, 0, 0, 0
BEGIN DESCRIPTION:
Multiple Run
END DESCRIPTION:

--- LITTLE LLANO 043.f01 (steady flow) ---

Flow Title=Multiple
Number of Profiles=7
Profile Names=10-year,25-year,50-year,1pct_min,100-year,1pct_plu,500-year
River Rch & RM= LITTLE LLANO 043,Reach-1,14728
     466     760    1187     885    1620    2965    2283
River Rch & RM= LITTLE LLANO 043,Reach-1,5038
     664    1109    1706    1230    2348    4480    3287
River Rch & RM= LITTLE LLANO 043,Reach-1,811
     712    1195    1823    1303    2512    4843    3513
Boundary for River Rch & Prof#=LITTLE LLANO 043,Reach-1,1
Up Type=0
Dn Type=3
Dn Slope=0.005
Boundary for River Rch & Prof#=LITTLE LLANO 043,Reach-1,2
Up Type=0
Dn Type=3
Dn Slope=0.005
Boundary for River Rch & Prof#=LITTLE LLANO 043,Reach-1,3
Up Type=0
Dn Type=3
Dn Slope=0.005
Boundary for River Rch & Prof#=LITTLE LLANO 043,Reach-1,4
Up Type=0
Dn Type=3
Dn Slope=0.005
Boundary for River Rch & Prof#=LITTLE LLANO 043,Reach-1,5
Up Type=0
Dn Type=3
Dn Slope=0.005
Boundary for River Rch & Prof#=LITTLE LLANO 043,Reach-1,6
Up Type=0
Dn Type=3
Dn Slope=0.005
Boundary for River Rch & Prof#=LITTLE LLANO 043,Reach-1,7
Up Type=0
Dn Type=3
Dn Slope=0.005

--- LITTLE LLANO 043.g01 (geometry) ---

Geom Title=Existing Conditions

River Reach=LITTLE LLANO 043,Reach-1
Reach XY= 30
      2812978.50     10265063.00      2813123.00     10264548.00
      2814274.00     10263800.00      2814558.00     10263308.00
      2814547.00     10263085.00      2815419.75     10262878.00
      2815550.75     10262769.00      2816182.50     10262698.00
      2816654.75     10262358.00      2816629.00     10262230.00
      2817043.75     10262007.00      2817364.75     10261172.00
      2817307.25     10261021.00      2817429.25     10260547.00
      2817285.75     10260083.00      2817437.50     10259992.00
      2817687.75     10260012.00      2817962.00     10259823.00
      2818023.50     10259444.00      2818461.50     10259257.00
      2818613.25     10258966.00      2819722.25     10258675.00
      2820193.00     10258753.00      2820328.00     10258664.00
      2820640.00     10258778.00      2821133.50     10258687.00
      2821520.75     10258466.00      2822067.50     10258378.00
      2822391.00     10258010.00      2823048.50     10258307.00

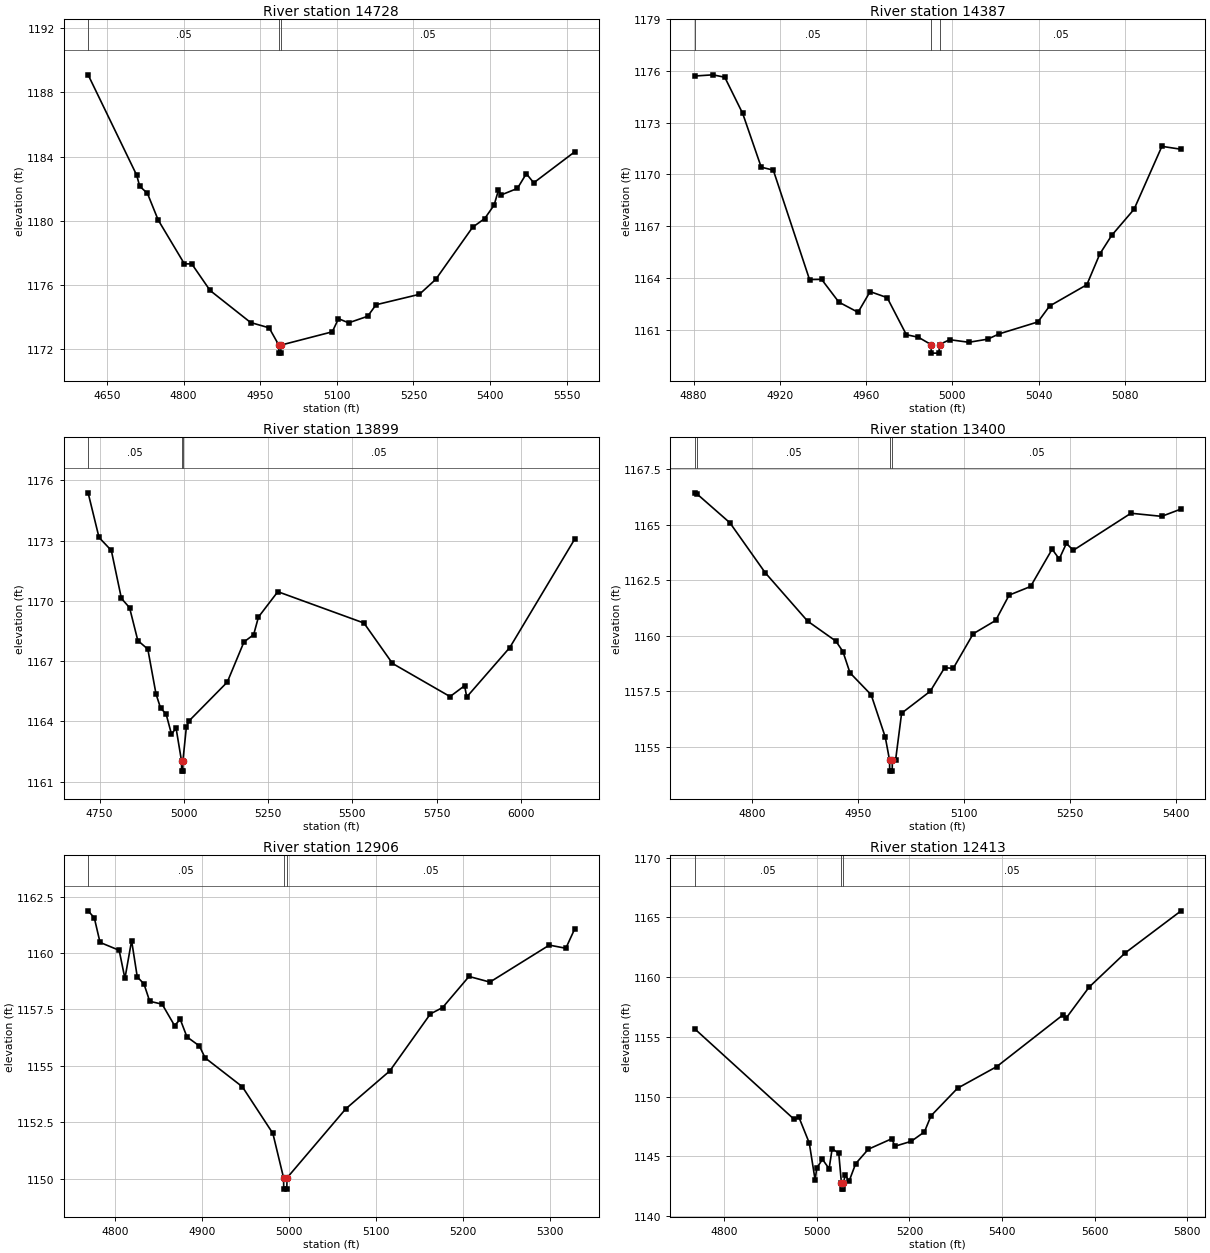
Type RM Length L Ch R = 1,14728,341,341,341
BEGIN DESCRIPTION:
LITTLE LLANO 043 29.0
END DESCRIPTION:
XS GIS Cut Line= 3
      2813255.68     10265103.10      2813044.00     10264779.00
      2812505.66     10264953.12
#Sta/Elev= 30
  4612.9 1189.10  4708.0 1182.84  4713.9 1182.15  4729.1 1181.70  4750.1 1180.04
  4801.5 1177.30  4815.9 1177.30  4851.8 1175.64  4931.2 1173.64  4967.4 1173.31
  4986.4 1172.23  4986.7 1171.73  4990.2 1171.73  4990.4 1172.23  5091.1 1173.06
  5103.3 1173.88  5123.1 1173.62  5160.4 1174.03  5176.9 1174.75  5261.7 1175.40
  5293.7 1176.33  5366.1 1179.59  5389.7 1180.13  5408.1 1180.97  5416.5 1181.89
  5421.7 1181.60  5453.7 1182.01  5471.2 1182.93  5485.7 1182.36  5565.8 1184.29
#Mann=3,-1,0
  4612.9    0.05       0  4986.4    0.03       0  4990.4    0.05       0
Bank Sta=4986.4,4990.4
Exp/Cntr=0.3,0.1

Type RM Length L Ch R = 1,14387,488,488,488
BEGIN DESCRIPTION:
LITTLE LLANO 043 28.0
END DESCRIPTION:
XS GIS Cut Line= 3
      2813255.69     10264603.13      2813202.75     10264496.00
      2813105.70     10264453.12
#Sta/Elev= 30
  4880.5 1175.71  4889.0 1175.78  4894.5 1175.64  4902.8 1173.54  4911.4 1170.42
  4917.0 1170.25  4933.8 1163.90  4939.4 1163.91  4947.4 1162.59  4956.3 1162.00
  4961.9 1163.20  4969.8 1162.85  4978.7 1160.70  4984.3 1160.55  4990.1 1160.13
  4990.3 1159.63  4993.8 1159.63  4994.1 1160.13  4998.8 1160.41  5007.7 1160.26
  5016.4 1160.44  5021.8 1160.75  5039.7 1161.44  5045.1 1162.36  5062.4 1163.60
  5068.4 1165.38  5073.9 1166.46  5084.3 1167.98  5097.2 1171.63  5106.1 1171.46
#Mann=3,-1,0
  4880.5    0.05       0  4990.1    0.03       0  4994.1    0.05       0
Bank Sta=4990.1,4994.1
Exp/Cntr=0.3,0.1

Type RM Length L Ch R = 1,13899,499,499,499
BEGIN DESCRIPTION:
LITTLE LLANO 043 27.0
END DESCRIPTION:
XS GIS Cut Line= 3
      2813705.68     10264553.10      2813601.25     10264289.00
      2812705.70     10263553.13
#Sta/Elev= 30
  4716.0 1175.38  4748.3 1173.16  4784.9 1172.51  4814.7 1170.13  4839.0 1169.66
  4863.4 1168.03  4893.1 1167.60  4917.4 1165.37  4931.1 1164.66  4947.2 1164.38
  4963.3 1163.37  4976.9 1163.67  4993.1 1162.03  4993.4 1161.53  4996.9 1161.53
  4997.1 1162.03  5007.5 1163.73  5015.4 1164.03  5128.8 1165.96  5178.3 1167.96
  5207.0 1168.32  5221.3 1169.20  5278.7 1170.46  5534.2 1168.90  5618.8 1166.89
  5789.6 1165.24  5832.7 1165.78  5839.1 1165.22  5966.8 1167.68  6159.1 1173.07
#Mann=3,-1,0
  4716.0    0.05       0  4993.1    0.05       0  4997.1    0.05       0
Bank Sta=4993.1,4997.1
Exp/Cntr=0.3,0.1

Type RM Length L Ch R = 1,13400,494,494,494
BEGIN DESCRIPTION:
LITTLE LLANO 043 26.0
END DESCRIPTION:
XS GIS Cut Line= 3
      2814005.68     10264303.09      2814007.50     10264022.00
      2813605.66     10263953.11
#Sta/Elev= 30
  4718.9 1166.44  4723.0 1166.37  4768.9 1165.09  4818.9 1162.84  4878.9 1160.66
  4918.9 1159.76  4928.9 1159.29  4938.9 1158.33  4968.9 1157.34  4988.9 1155.43
  4994.9 1154.40  4995.2 1153.90  4998.7 1153.90  4998.9 1154.40  5003.5 1154.40
  5012.0 1156.51  5052.6 1157.50  5072.9 1158.56  5085.1 1158.53  5113.4 1160.09
  5145.2 1160.69  5164.2 1161.83  5194.6 1162.22  5225.1 1163.90  5235.2 1163.46
  5245.3 1164.16  5255.1 1163.85  5336.7 1165.52  5380.2 1165.38  5407.7 1165.71
#Mann=4,-1,0
  4718.9    0.12       0  4723.0    0.05       0  4994.9    0.05       0
  4998.9    0.05       0
Bank Sta=4994.9,4998.9
Exp/Cntr=0.3,0.1

Type RM Length L Ch R = 1,12906,493,493,493
BEGIN DESCRIPTION:
LITTLE LLANO 043 25.0
END DESCRIPTION:
XS GIS Cut Line= 3
      2814505.69     10263853.12      2814330.25     10263703.00
      2814005.66     10263653.11
#Sta/Elev= 30
  4769.1 1161.87  4776.2 1161.56  4782.8 1160.47  4804.8 1160.12  4811.4 1158.87
  4819.1 1160.55  4825.6 1158.94  4833.3 1158.63  4839.9 1157.86  4854.2 1157.73
  4868.5 1156.78  4875.0 1157.06  4882.7 1156.28  4897.0 1155.88  4903.6 1155.35
  4946.4 1154.07  4981.5 1152.00  4993.8 1150.03  4994.0 1149.53  4997.5 1149.53
  4997.8 1150.03  5065.3 1153.09  5115.9 1154.77  5162.6 1157.30  5176.6 1157.58
  5207.0 1158.96  5231.0 1158.71  5299.3 1160.35  5318.3 1160.21  5328.4 1161.06
#Mann=3,-1,0
  4769.1    0.05       0  4993.8    0.05       0  4997.8    0.05       0
Bank Sta=4993.8,4997.8
Exp/Cntr=0.3,0.1

Type RM Length L Ch R = 1,12413,499,499,499
BEGIN DESCRIPTION:
LITTLE LLANO 043 24.0
END DESCRIPTION:
XS GIS Cut Line= 3
      2814655.70     10263553.15      2814558.00     10263308.00
      2814055.66     10262703.08
#Sta/Elev= 30
  4736.1 1155.68  4951.4 1148.08  4961.3 1148.27  4983.7 1146.11  4996.3 1143.01
  4999.9 1144.03  5012.2 1144.74  5026.5 1143.96  5033.0 1145.62  5047.3 1145.27
  5053.1 1142.75  5053.4 1142.25  5056.9 1142.25  5057.1 1142.75  5061.6 1143.44
  5069.5 1142.90  5083.8 1144.38  5111.1 1145.59  5161.9 1146.47  5168.4 1145.84
  5203.6 1146.25  5232.2 1147.04  5246.5 1148.39  5303.8 1150.70  5388.5 1152.51
  5530.4 1156.81  5538.2 1156.57  5587.7 1159.16  5665.8 1162.03  5786.3 1165.55
#Mann=3,-1,0
  4736.1    0.05       0  5053.1    0.05       0  5057.1    0.05       0
Bank Sta=5053.1,5057.1
Exp/Cntr=0.3,0.1

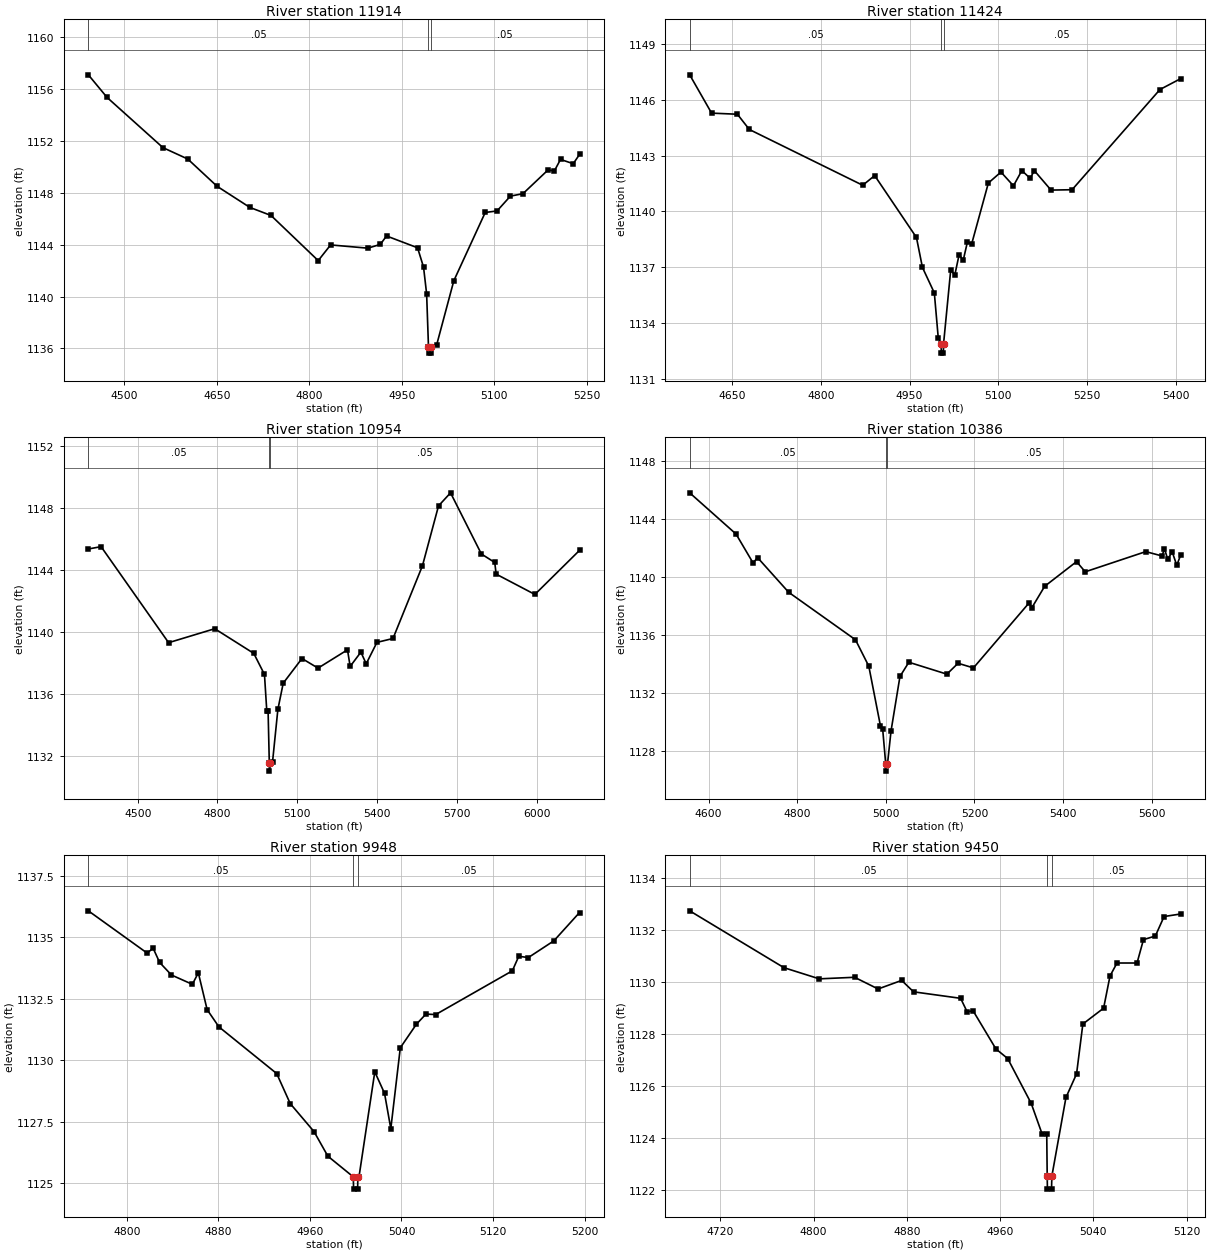
Type RM Length L Ch R = 1,11914,490,490,490
BEGIN DESCRIPTION:
LITTLE LLANO 043 23.0
END DESCRIPTION:
XS GIS Cut Line= 3
      2814855.69     10263553.16      2814789.50     10262999.00
      2814555.66     10262953.11
#Sta/Elev= 30
  4441.9 1157.09  4472.2 1155.35  4562.8 1151.48  4603.1 1150.60  4650.6 1148.50
  4703.8 1146.87  4738.1 1146.25  4814.6 1142.77  4834.7 1143.98  4895.1 1143.73
  4915.3 1144.02  4925.4 1144.67  4975.7 1143.76  4985.4 1142.27  4990.4 1140.21
  4993.4 1136.14  4993.7 1135.64  4997.2 1135.64  4997.4 1136.14  5006.8 1136.30
  5034.5 1141.22  5085.4 1146.48  5104.6 1146.60  5126.2 1147.74  5146.6 1147.93
  5187.3 1149.76  5197.5 1149.68  5207.5 1150.57  5228.1 1150.24  5238.3 1150.95
#Mann=3,-1,0
  4441.9    0.05       0  4993.4    0.05       0  4997.4    0.05       0
Bank Sta=4993.4,4997.4
Exp/Cntr=0.3,0.1

Type RM Length L Ch R = 1,11424,470,470,470
BEGIN DESCRIPTION:
LITTLE LLANO 043 22.0
END DESCRIPTION:
XS GIS Cut Line= 3
      2815305.68     10263303.07      2815251.25     10262885.00
      2814955.71     10262603.14
#Sta/Elev= 30
  4578.4 1147.35  4615.4 1145.29  4659.0 1145.23  4679.2 1144.41  4870.8 1141.41
  4891.0 1141.93  4961.6 1138.60  4971.7 1136.99  4991.8 1135.62  4998.4 1133.21
  5003.4 1132.88  5003.6 1132.38  5007.1 1132.38  5007.4 1132.88  5019.5 1136.85
  5026.4 1136.58  5033.7 1137.68  5040.6 1137.37  5047.8 1138.37  5054.8 1138.24
  5083.1 1141.53  5104.4 1142.12  5125.5 1141.38  5139.7 1142.20  5153.8 1141.78
  5160.7 1142.20  5189.0 1141.15  5224.6 1141.17  5373.1 1146.56  5408.4 1147.15
#Mann=3,-1,0
  4578.4    0.05       0  5003.4    0.05       0  5007.4    0.05       0
Bank Sta=5003.4,5007.4
Exp/Cntr=0.3,0.1

Type RM Length L Ch R = 1,10954,568,568,568
BEGIN DESCRIPTION:
LITTLE LLANO 043 21.0
END DESCRIPTION:
XS GIS Cut Line= 3
      2815889.57     10263451.45      2815674.39     10262938.14
      2815524.22     10261656.49
#Sta/Elev= 30
  4314.4 1145.35  4362.3 1145.50  4616.2 1139.31  4789.7 1140.21  4936.5 1138.62
  4976.7 1137.26  4985.3 1134.93  4990.3 1134.92  4994.9 1131.53  4995.1 1131.03
  4998.9 1131.53  5006.9 1131.60  5027.1 1135.01  5047.2 1136.70  5117.7 1138.29
  5178.1 1137.67  5288.9 1138.85  5298.9 1137.78  5339.2 1138.70  5359.3 1137.95
  5399.6 1139.33  5460.0 1139.58  5570.8 1144.27  5631.2 1148.13  5676.4 1148.97
  5792.3 1145.03  5842.6 1144.48  5847.9 1143.73  5993.6 1142.42  6161.4 1145.26
#Mann=3,-1,0
  4314.4    0.05       0  4994.9    0.05       0  4998.9    0.05       0
Bank Sta=4994.9,4998.9
Exp/Cntr=0.3,0.1

Type RM Length L Ch R = 1,10386,438,438,438
BEGIN DESCRIPTION:
LITTLE LLANO 043 20.0
END DESCRIPTION:
XS GIS Cut Line= 3
      2816179.89     10263145.53      2816127.15     10262567.18
      2816249.87     10262054.21
#Sta/Elev= 30
  4557.5 1145.80  4662.1 1142.96  4700.5 1140.97  4710.6 1141.34  4780.8 1138.95
  4931.5 1135.68  4961.6 1133.86  4988.0 1129.73  4993.0 1129.50  4999.8 1127.13
  5000.0 1126.63  5003.8 1127.13  5011.8 1129.40  5031.9 1133.15  5052.0 1134.13
  5137.8 1133.31  5163.0 1134.06  5197.7 1133.74  5323.9 1138.24  5329.0 1137.86
  5358.4 1139.36  5430.3 1141.06  5450.0 1140.36  5586.5 1141.75  5623.4 1141.45
  5628.5 1141.96  5636.0 1141.24  5646.3 1141.72  5656.5 1140.81  5665.7 1141.55
#Mann=3,-1,0
  4557.5    0.05       0  4999.8    0.05       0  5003.8    0.05       0
Bank Sta=4999.8,5003.8
Exp/Cntr=0.3,0.1

Type RM Length L Ch R = 1,9948,498,498,498
BEGIN DESCRIPTION:
LITTLE LLANO 043 19.0
END DESCRIPTION:
XS GIS Cut Line= 3
      2816555.68     10262703.10      2816493.25     10262478.00
      2816405.68     10262303.10
#Sta/Elev= 30
  4766.4 1136.08  4817.8 1134.36  4823.0 1134.56  4828.7 1133.98  4839.0 1133.47
  4857.3 1133.09  4862.5 1133.56  4870.2 1132.06  4880.5 1131.36  4931.0 1129.46
  4942.8 1128.24  4963.6 1127.10  4975.7 1126.10  4997.9 1125.26  4998.2 1124.76
  5001.7 1124.76  5001.9 1125.26  5002.9 1125.26  5016.7 1129.53  5025.2 1128.66
  5030.7 1127.22  5039.0 1130.51  5053.1 1131.47  5061.4 1131.88  5069.9 1131.86
  5136.9 1133.64  5142.5 1134.23  5150.9 1134.18  5173.2 1134.86  5195.6 1136.01
#Mann=3,-1,0
  4766.4    0.05       0  4997.9    0.03       0  5001.9    0.05       0
Bank Sta=4997.9,5001.9
Exp/Cntr=0.3,0.1

Type RM Length L Ch R = 1,9450,497,497,497
BEGIN DESCRIPTION:
LITTLE LLANO 043 18.0
END DESCRIPTION:
XS GIS Cut Line= 3
      2816805.68     10262503.09      2816760.75     10262200.00
      2816655.64     10262153.09
#Sta/Elev= 30
  4693.6 1132.75  4774.5 1130.56  4804.8 1130.13  4835.1 1130.19  4855.3 1129.74
  4875.5 1130.07  4885.7 1129.63  4926.1 1129.38  4931.7 1128.86  4936.8 1128.90
  4956.4 1127.43  4966.5 1127.06  4986.7 1125.33  4995.9 1124.17  5000.0 1124.17
  5000.4 1122.53  5000.6 1122.03  5004.1 1122.03  5004.4 1122.53  5016.5 1125.56
  5025.6 1126.47  5031.0 1128.39  5048.8 1129.00  5054.3 1130.24  5060.3 1130.74
  5077.5 1130.74  5083.0 1131.64  5093.2 1131.78  5100.7 1132.53  5115.1 1132.63
#Mann=3,-1,0
  4693.6    0.05       0  5000.4    0.03       0  5004.4    0.05       0
Bank Sta=5000.4,5004.4
Exp/Cntr=0.3,0.1

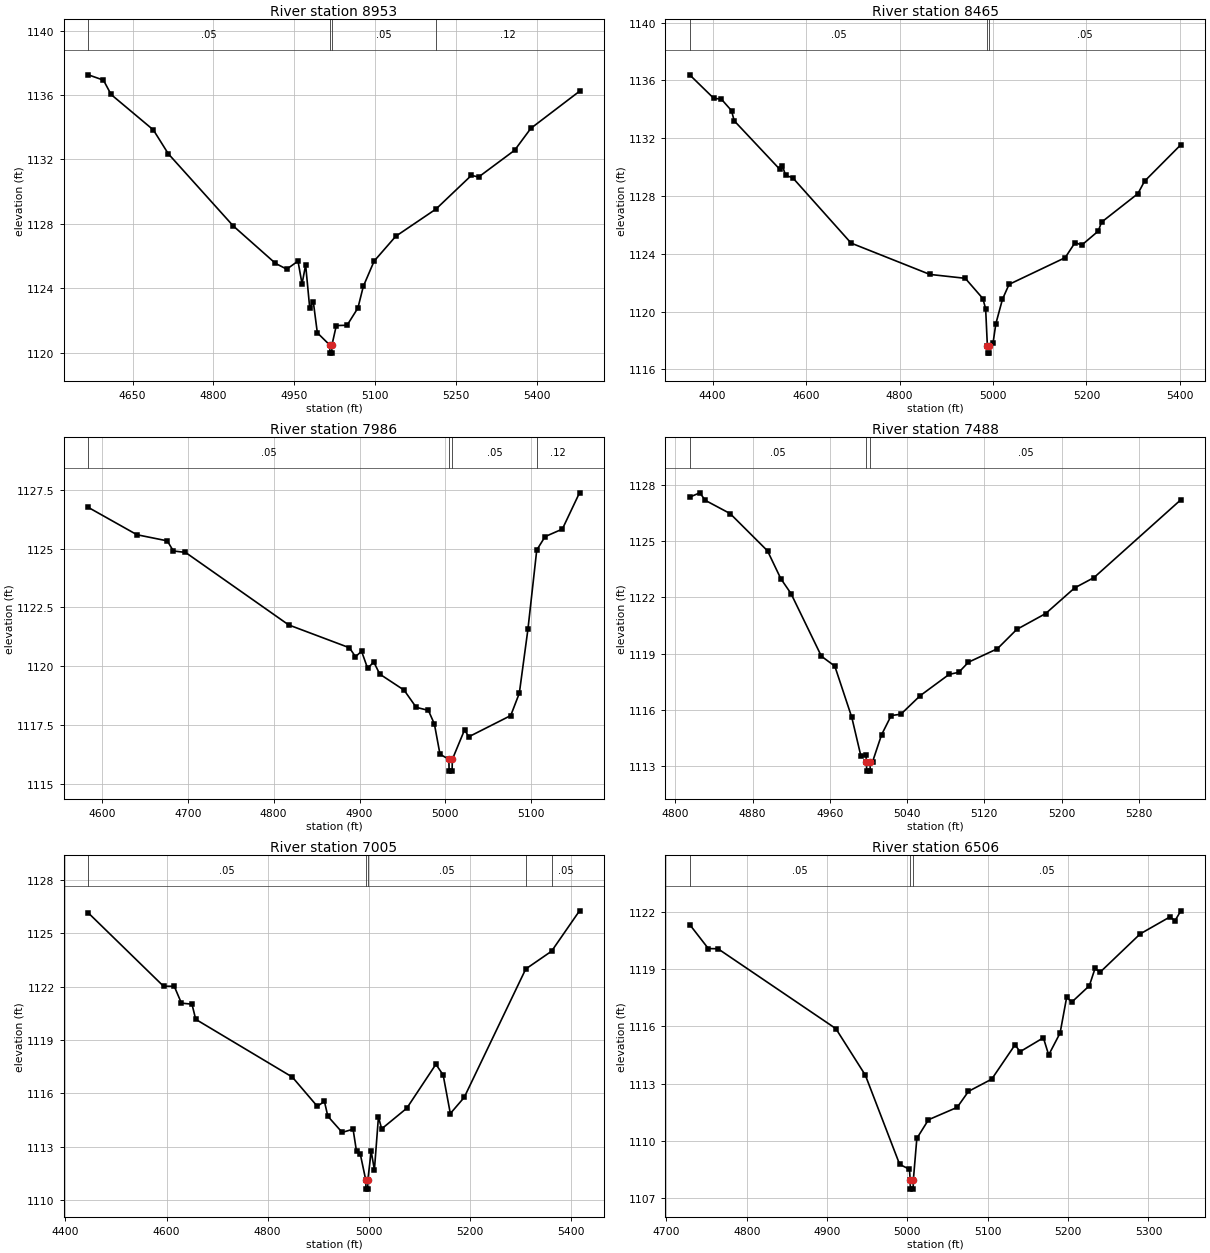
Type RM Length L Ch R = 1,8953,488,488,488
BEGIN DESCRIPTION:
LITTLE LLANO 043 17.0
END DESCRIPTION:
XS GIS Cut Line= 3
      2817405.66     10262153.09      2817083.75     10261865.00
      2816605.67     10261903.11
#Sta/Elev= 30
  4568.0 1137.25  4596.0 1136.92  4610.2 1136.03  4688.7 1133.83  4716.4 1132.35
  4836.7 1127.88  4915.3 1125.55  4936.2 1125.19  4957.1 1125.69  4964.6 1124.28
  4971.3 1125.45  4978.8 1122.80  4985.5 1123.17  4993.0 1121.24  5016.1 1120.48
  5016.4 1119.98  5019.9 1119.98  5020.1 1120.48  5028.2 1121.69  5048.2 1121.71
  5068.3 1122.78  5078.3 1124.12  5098.4 1125.69  5138.5 1127.23  5213.2 1128.92
  5278.9 1131.01  5292.4 1130.91  5359.2 1132.57  5389.3 1133.93  5479.6 1136.23
#Mann=4,-1,0
  4568.0    0.05       0  5016.1    0.03       0  5020.1    0.05       0
  5213.2    0.12       0
Bank Sta=5016.1,5020.1
Exp/Cntr=0.3,0.1

Type RM Length L Ch R = 1,8465,479,479,479
BEGIN DESCRIPTION:
LITTLE LLANO 043 16.0
END DESCRIPTION:
XS GIS Cut Line= 3
      2817555.67     10262003.08      2817243.25     10261434.00
      2816955.67     10261153.10
#Sta/Elev= 30
  4350.8 1136.39  4402.4 1134.76  4418.5 1134.71  4440.3 1133.91  4446.0 1133.21
  4543.6 1129.85  4549.3 1130.09  4556.1 1129.42  4571.1 1129.27  4696.2 1124.74
  4864.8 1122.57  4940.6 1122.30  4978.2 1120.90  4984.2 1120.19  4987.9 1117.62
  4988.2 1117.12  4991.7 1117.12  4991.9 1117.62  5000.0 1117.81  5006.0 1119.15
  5020.2 1120.85  5034.3 1121.88  5154.4 1123.73  5175.7 1124.78  5189.9 1124.60
  5225.2 1125.57  5232.3 1126.19  5310.0 1128.16  5324.2 1129.02  5402.0 1131.55
#Mann=3,-1,0
  4350.8    0.05       0  4987.9    0.05       0  4991.9    0.05       0
Bank Sta=4987.9,4991.9
Exp/Cntr=0.3,0.1

Type RM Length L Ch R = 1,7986,498,498,498
BEGIN DESCRIPTION:
LITTLE LLANO 043 15.0
END DESCRIPTION:
XS GIS Cut Line= 3
      2817605.68     10261303.10      2817311.75     10261009.00
      2817155.66     10261003.11
#Sta/Elev= 30
  4584.2 1126.75  4640.8 1125.59  4676.1 1125.33  4683.2 1124.90  4697.3 1124.84
  4817.5 1121.76  4888.2 1120.79  4895.3 1120.41  4902.4 1120.64  4909.5 1119.91
  4916.5 1120.19  4923.6 1119.67  4951.9 1118.99  4966.0 1118.26  4980.2 1118.13
  4987.2 1117.55  4993.7 1116.27  5004.1 1116.05  5004.3 1115.55  5007.8 1115.55
  5008.1 1116.05  5022.3 1117.30  5027.3 1117.01  5076.1 1117.91  5086.1 1118.86
  5096.1 1121.57  5106.4 1124.94  5116.1 1125.51  5136.2 1125.83  5156.2 1127.37
#Mann=4,-1,0
  4584.2    0.05       0  5004.1    0.05       0  5008.1    0.05       0
  5106.4    0.12       0
Bank Sta=5004.1,5008.1
Exp/Cntr=0.3,0.1

Type RM Length L Ch R = 1,7488,483,483,483
BEGIN DESCRIPTION:
LITTLE LLANO 043 14.0
END DESCRIPTION:
XS GIS Cut Line= 3
      2817605.64     10260603.10      2817429.25     10260547.00
      2817105.71     10260553.11
#Sta/Elev= 30
  4814.9 1127.36  4825.4 1127.59  4831.0 1127.19  4856.8 1126.48  4895.5 1124.49
  4909.3 1123.00  4919.8 1122.21  4951.3 1118.86  4965.2 1118.33  4982.8 1115.59
  4992.2 1113.53  4997.4 1113.58  4998.0 1113.22  4998.2 1112.72  5001.7 1112.72
  5002.0 1113.22  5004.3 1113.22  5013.6 1114.66  5023.6 1115.69  5033.6 1115.76
  5053.6 1116.75  5083.6 1117.89  5093.6 1118.00  5103.6 1118.54  5133.6 1119.26
  5153.6 1120.29  5183.6 1121.14  5213.6 1122.51  5233.6 1123.06  5323.6 1127.22
#Mann=3,-1,0
  4814.9    0.05       0  4998.0    0.05       0  5002.0    0.05       0
Bank Sta=4998,5002
Exp/Cntr=0.3,0.1

Type RM Length L Ch R = 1,7005,499,499,499
BEGIN DESCRIPTION:
LITTLE LLANO 043 13.0
END DESCRIPTION:
XS GIS Cut Line= 3
      2817655.71     10260503.14      2817282.25     10260093.00
      2816955.68     10260353.11
#Sta/Elev= 30
  4445.3 1126.15  4594.1 1122.03  4615.3 1122.03  4629.5 1121.08  4650.4 1121.02
  4657.8 1120.17  4849.1 1116.92  4898.4 1115.28  4912.6 1115.55  4919.3 1114.72
  4947.7 1113.81  4969.3 1113.99  4976.1 1112.74  4983.5 1112.60  4994.5 1111.12
  4994.8 1110.62  4998.3 1110.62  4998.5 1111.12  5005.1 1112.76  5011.5 1111.70
  5019.5 1114.68  5025.9 1114.01  5075.6 1115.17  5133.2 1117.64  5147.6 1117.04
  5161.8 1114.87  5189.3 1115.78  5311.1 1123.00  5362.2 1124.00  5417.5 1126.27
#Mann=5,-1,0
  4445.3    0.05       0  4994.5    0.05       0  4998.5    0.05       0
  5311.1    0.12       0  5362.2    0.05       0
Bank Sta=4994.5,4998.5
Exp/Cntr=0.3,0.1

Type RM Length L Ch R = 1,6506,490,490,490
BEGIN DESCRIPTION:
LITTLE LLANO 043 12.0
END DESCRIPTION:
XS GIS Cut Line= 3
      2817855.71     10260203.15      2817714.25     10259972.00
      2817505.68     10259703.11
#Sta/Elev= 30
  4729.0 1121.34  4752.2 1120.08  4764.2 1120.07  4910.9 1115.88  4947.6 1113.44
  4990.3 1108.76  5002.5 1108.50  5003.4 1107.96  5003.6 1107.46  5007.1 1107.46
  5007.4 1107.96  5011.7 1110.12  5026.2 1111.10  5061.9 1111.75  5076.0 1112.59
  5104.9 1113.23  5133.9 1115.03  5140.2 1114.67  5169.2 1115.40  5175.8 1114.50
  5190.0 1115.65  5198.2 1117.53  5204.5 1117.27  5226.4 1118.13  5233.5 1119.04
  5239.8 1118.84  5289.7 1120.85  5326.7 1121.74  5333.1 1121.55  5340.3 1122.06
#Mann=3,-1,0
  4729.0    0.05       0  5003.4    0.05       0  5007.4    0.05       0
Bank Sta=5003.4,5007.4
Exp/Cntr=0.3,0.1

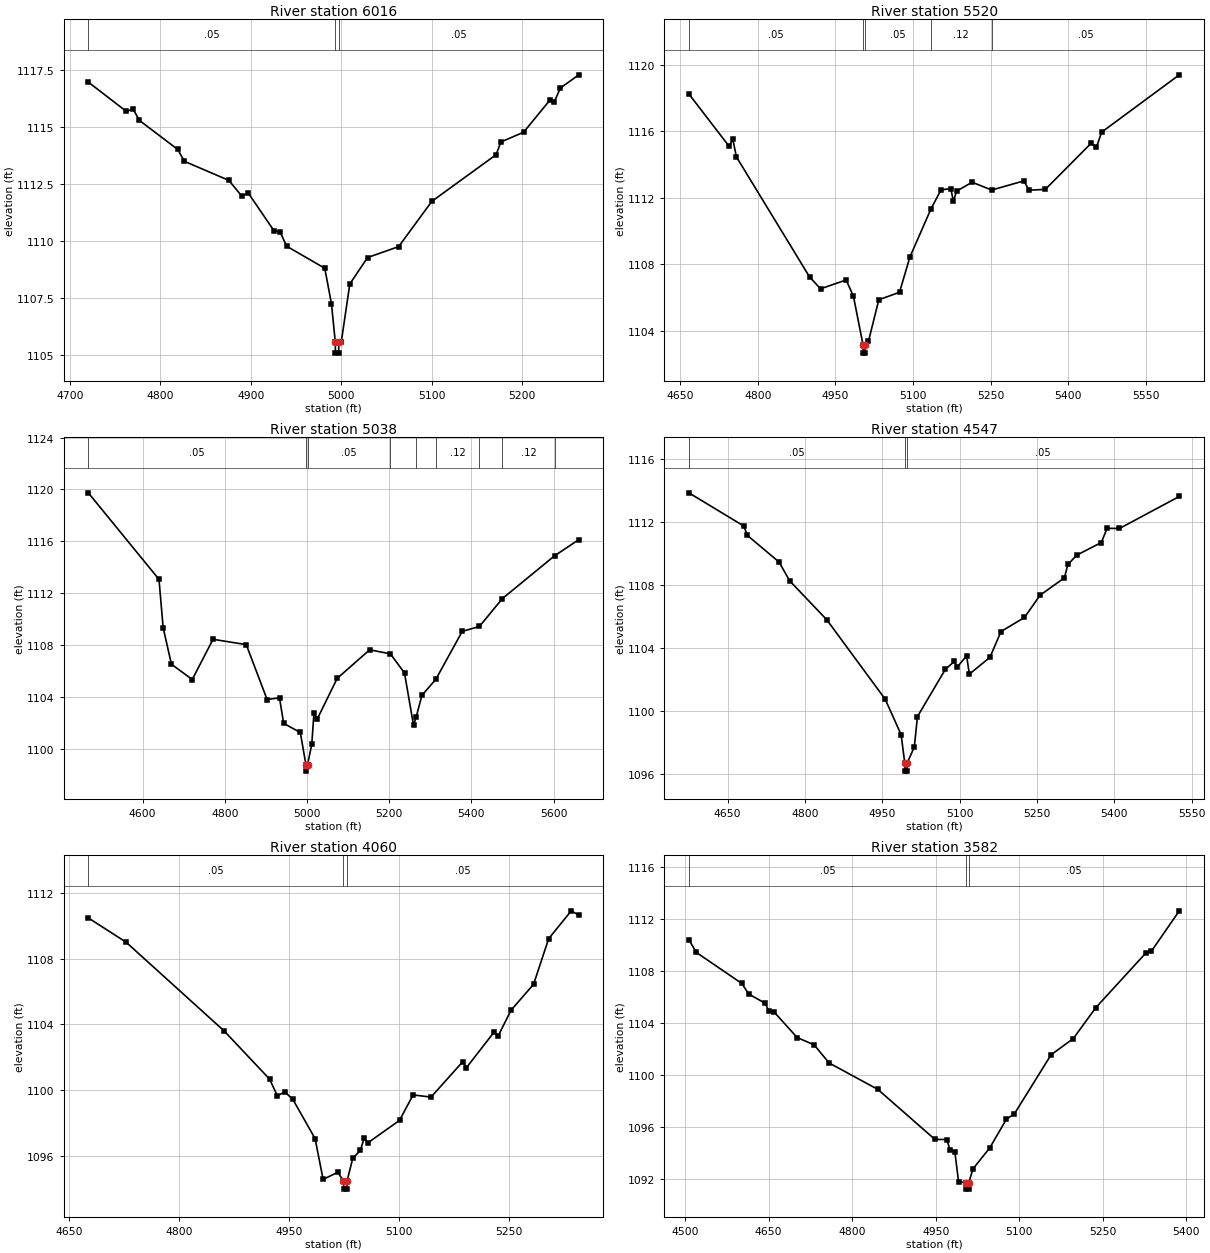
Type RM Length L Ch R = 1,6016,496,496,496
BEGIN DESCRIPTION:
LITTLE LLANO 043 11.0
END DESCRIPTION:
XS GIS Cut Line= 3
      2818205.66     10259853.08      2818014.25     10259649.00
      2817755.69     10259603.11
#Sta/Elev= 30
  4720.2 1116.98  4762.4 1115.69  4769.7 1115.80  4776.6 1115.30  4819.1 1114.02
  4826.4 1113.50  4875.7 1112.66  4889.9 1111.97  4897.2 1112.10  4925.5 1110.45
  4932.4 1110.39  4939.5 1109.77  4981.7 1108.80  4989.1 1107.24  4993.3 1105.57
  4993.5 1105.07  4997.0 1105.07  4997.3 1105.57  5000.0 1105.57  5009.4 1108.11
  5029.0 1109.27  5063.4 1109.75  5100.1 1111.74  5171.2 1113.79  5176.5 1114.35
  5201.7 1114.78  5230.5 1116.18  5235.6 1116.12  5242.3 1116.72  5262.6 1117.30
#Mann=3,-1,0
  4720.2    0.05       0  4993.3    0.05       0  4997.3    0.05       0
Bank Sta=4993.3,4997.3
Exp/Cntr=0.3,0.1

Type RM Length L Ch R = 1,5520,482,482,482
BEGIN DESCRIPTION:
LITTLE LLANO 043 10.0
END DESCRIPTION:
XS GIS Cut Line= 3
      2818505.71     10259553.14      2818269.50     10259318.00
      2817655.70     10259353.11
#Sta/Elev= 30
  4666.7 1118.24  4744.5 1115.09  4751.6 1115.52  4758.7 1114.45  4900.1 1107.23
  4921.3 1106.52  4970.8 1107.05  4984.9 1106.06  5003.4 1103.15  5003.6 1102.65
  5007.1 1102.65  5007.4 1103.15  5013.8 1103.35  5033.9 1105.86  5073.9 1106.31
  5094.0 1108.43  5134.8 1111.33  5154.1 1112.47  5173.1 1112.55  5178.1 1111.78
  5184.1 1112.39  5214.2 1112.93  5252.1 1112.46  5314.3 1113.01  5324.3 1112.45
  5355.8 1112.50  5444.5 1115.28  5454.6 1115.04  5464.6 1115.94  5614.8 1119.39
#Mann=5,-1,0
  4666.7    0.05       0  5003.4    0.05       0  5007.4    0.05       0
  5134.8    0.12       0  5252.1    0.05       0
Bank Sta=5003.4,5007.4
Exp/Cntr=0.3,0.1

Type RM Length L Ch R = 1,5038,491,491,491
BEGIN DESCRIPTION:
LITTLE LLANO 043 9.0
END DESCRIPTION:
XS GIS Cut Line= 3
      2818655.68     10259553.09      2818575.25     10259027.00
      2818355.68     10258403.11
#Sta/Elev= 30
  4467.8 1119.74  4639.8 1113.07  4649.9 1109.35  4670.1 1106.53  4720.7 1105.35
  4771.3 1108.45  4852.2 1108.04  4902.9 1103.81  4933.1 1103.94  4943.2 1101.97
  4983.7 1101.27  4997.4 1098.79  4997.7 1098.29  5001.4 1098.79  5011.6 1100.36
  5016.9 1102.74  5025.3 1102.33  5073.5 1105.44  5152.5 1107.64  5203.0 1107.33
  5237.3 1105.85  5259.3 1101.82  5265.8 1102.48  5279.7 1104.13  5313.8 1105.38
  5377.8 1109.06  5419.6 1109.44  5475.6 1111.59  5602.7 1114.89  5661.4 1116.13
#Mann=9,-1,0
  4467.8    0.05       0  4997.4    0.03       0  5001.4    0.05       0
  5203.0    0.12       0  5265.8    0.05       0  5313.8    0.12       0
  5419.6    0.05       0  5475.6    0.12       0  5602.7    0.05       0
Bank Sta=4997.4,5001.4
Exp/Cntr=0.3,0.1

Type RM Length L Ch R = 1,4547,487,487,487
BEGIN DESCRIPTION:
LITTLE LLANO 043 8.0
END DESCRIPTION:
XS GIS Cut Line= 3
      2819105.68     10259253.11      2819005.00     10258840.00
      2818805.69     10258353.12
#Sta/Elev= 30
  4574.8 1113.85  4681.6 1111.74  4688.0 1111.16  4749.8 1109.46  4770.4 1108.27
  4842.4 1105.80  4955.6 1100.77  4986.5 1098.52  4993.6 1096.71  4993.9 1096.21
  4997.8 1096.21  4998.1 1096.71  5012.1 1097.74  5018.2 1099.67  5072.3 1102.66
  5089.5 1103.16  5094.9 1102.79  5113.5 1103.52  5118.9 1102.36  5158.7 1103.42
  5180.3 1105.06  5225.8 1105.95  5256.0 1107.36  5303.2 1108.46  5310.0 1109.31
  5327.2 1109.90  5374.8 1110.70  5386.0 1111.60  5410.0 1111.59  5526.1 1113.62
#Mann=3,-1,0
  4574.8    0.05       0  4993.6    0.03       0  4998.1    0.05       0
Bank Sta=4993.6,4998.1
Exp/Cntr=0.3,0.1

Type RM Length L Ch R = 1,4060,478,478,478
BEGIN DESCRIPTION:
LITTLE LLANO 043 7.0
END DESCRIPTION:
XS GIS Cut Line= 3
      2819555.68     10259103.08      2819479.00     10258789.00
      2819555.68     10258453.14
#Sta/Elev= 30
  4676.7 1110.46  4728.1 1108.99  4861.6 1103.61  4923.7 1100.68  4934.0 1099.68
  4944.3 1099.91  4955.2 1099.46  4985.5 1097.08  4996.4 1094.61  5016.3 1095.04
  5024.1 1094.52  5024.5 1094.02  5028.7 1094.02  5029.0 1094.52  5036.8 1095.89
  5047.1 1096.37  5052.3 1097.10  5057.5 1096.83  5100.5 1098.19  5118.9 1099.73
  5143.4 1099.60  5186.4 1101.74  5191.5 1101.38  5229.4 1103.55  5234.5 1103.28
  5252.2 1104.86  5283.0 1106.44  5303.5 1109.20  5334.3 1110.89  5344.5 1110.63
#Mann=3,-1,0
  4676.7    0.05       0  5024.1    0.05       0  5029.0    0.05       0
Bank Sta=5024.1,5029
Exp/Cntr=0.3,0.1

Type RM Length L Ch R = 1,3582,486,486,486
BEGIN DESCRIPTION:
LITTLE LLANO 043 6.0
END DESCRIPTION:
XS GIS Cut Line= 3
      2819655.67     10259103.13      2819925.25     10258690.00
      2819905.68     10258303.09
#Sta/Elev= 30
  4506.7 1110.40  4520.2 1109.41  4601.8 1107.03  4614.2 1106.22  4644.0 1105.50
  4650.0 1104.93  4659.1 1104.87  4701.3 1102.87  4731.5 1102.32  4758.6 1100.92
  4846.1 1098.89  4948.5 1095.05  4969.9 1095.04  4975.9 1094.21  4984.3 1094.11
  4991.0 1091.80  5004.4 1091.73  5004.8 1091.23  5009.0 1091.23  5009.3 1091.73
  5016.9 1092.79  5046.9 1094.39  5077.0 1096.61  5091.2 1097.01  5157.1 1101.55
  5197.1 1102.80  5237.2 1105.16  5327.3 1109.37  5337.3 1109.51  5387.4 1112.61
#Mann=3,-1,0
  4506.7    0.05       0  5004.4    0.05       0  5009.3    0.05       0
Bank Sta=5004.4,5009.3
Exp/Cntr=0.3,0.1

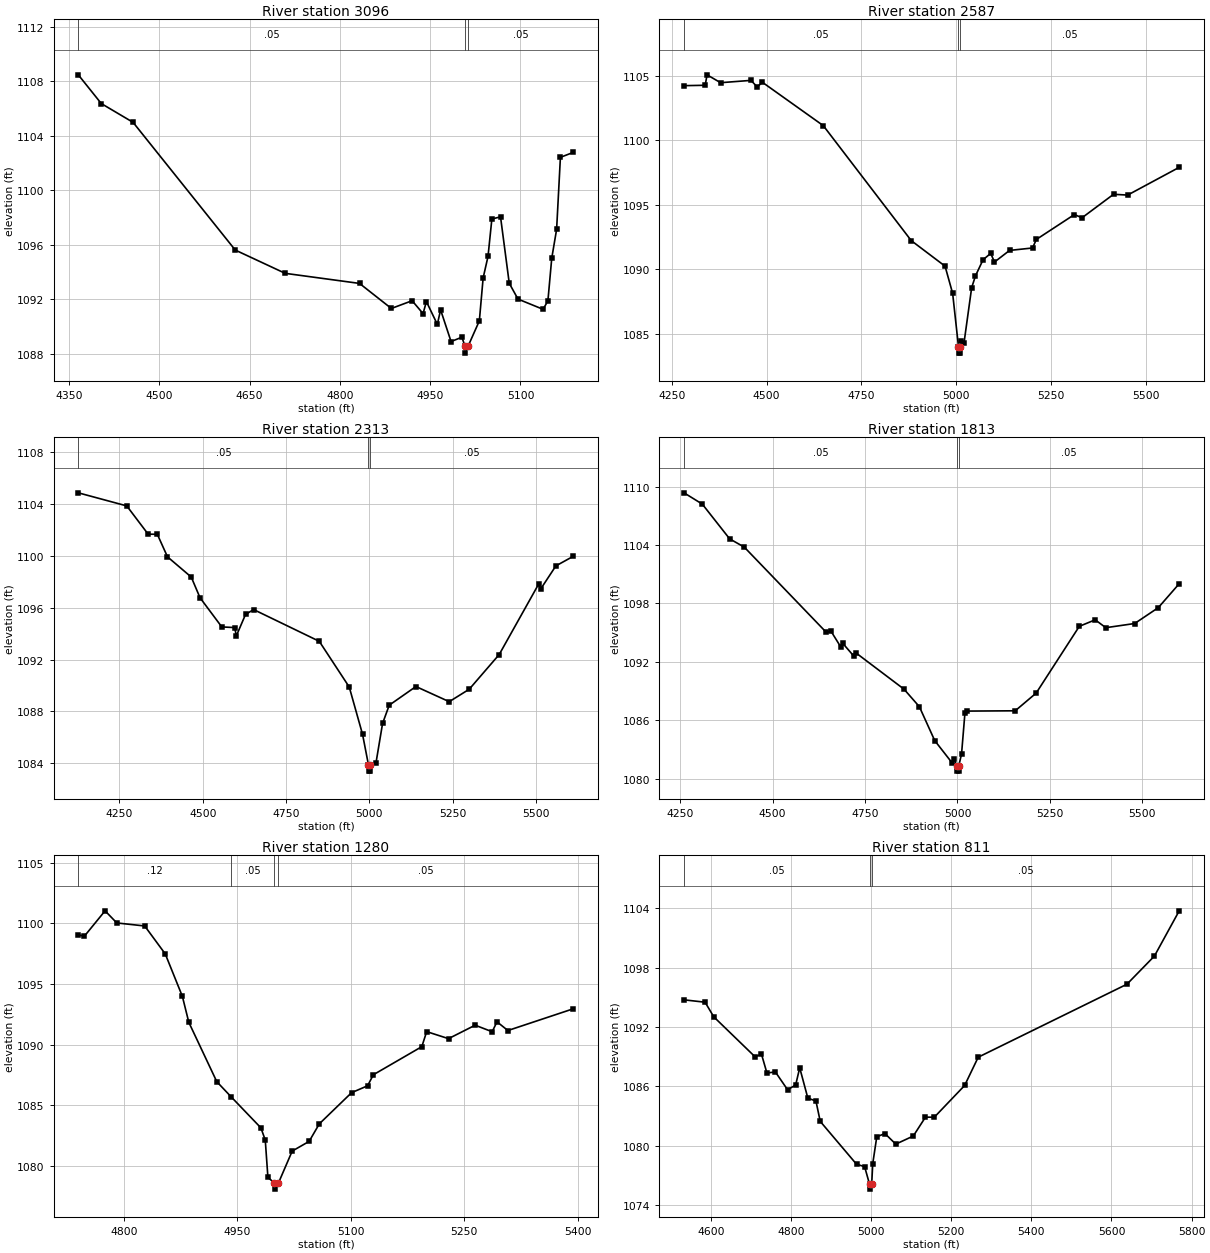
Type RM Length L Ch R = 1,3096,509,509,509
BEGIN DESCRIPTION:
LITTLE LLANO 043 5.0
END DESCRIPTION:
XS GIS Cut Line= 3
      2820605.70     10259253.16      2820357.50     10258669.00
      2820505.67     10258553.12
#Sta/Elev= 30
  4365.3 1108.47  4403.5 1106.36  4456.3 1104.98  4626.1 1095.60  4709.1 1093.89
  4832.6 1093.15  4885.5 1091.31  4920.0 1091.88  4938.2 1090.93  4943.7 1091.82
  4961.9 1090.14  4967.3 1091.21  4984.7 1088.88  5002.7 1089.20  5007.9 1088.53
  5008.2 1088.03  5012.9 1088.53  5031.7 1090.40  5038.0 1093.55  5046.1 1095.13
  5052.5 1097.88  5066.9 1098.04  5081.4 1093.16  5095.9 1092.00  5137.5 1091.25
  5145.6 1091.86  5152.0 1095.00  5160.1 1097.12  5166.4 1102.41  5188.1 1102.78
#Mann=3,-1,0
  4365.3    0.05       0  5007.9    0.05       0  5012.9    0.05       0
Bank Sta=5007.9,5012.9
Exp/Cntr=0.3,0.1

Type RM Length L Ch R = 1,2587,274,274,274
BEGIN DESCRIPTION:
Mapping XS 57bdb50c
END DESCRIPTION:
XS GIS Cut Line= 2
      2820895.19     10259469.14      2820797.58     10258167.59
#Sta/Elev= 30
  4282.3 1104.23  4338.0 1104.26  4343.0 1105.07  4378.6 1104.46  4458.8 1104.64
  4475.1 1104.13  4488.9 1104.49  4649.4 1101.13  4881.2 1092.22  4970.3 1090.24
  4990.3 1088.13  5005.7 1084.00  5006.1 1083.50  5010.4 1083.50  5010.8 1084.00
  5013.3 1084.44  5020.4 1084.32  5040.4 1088.57  5050.5 1089.49  5070.5 1090.74
  5090.6 1091.23  5100.6 1090.56  5140.3 1091.46  5200.9 1091.65  5210.9 1092.31
  5311.2 1094.24  5331.3 1093.99  5414.4 1095.81  5451.6 1095.75  5587.5 1097.90
#Mann=3,-1,0
  4282.3    0.05       0  5005.7    0.05       0  5010.8    0.05       0
Bank Sta=5005.7,5010.8
Exp/Cntr=0.3,0.1

Type RM Length L Ch R = 1,2313,500,500,500
BEGIN DESCRIPTION:
Mapping XS bab807e7
END DESCRIPTION:
XS GIS Cut Line= 3
      2821209.87     10259556.01      2821101.36     10258991.73
      2821123.06     10258080.31
#Sta/Elev= 30
  4126.5 1104.87  4272.0 1103.86  4336.1 1101.68  4363.7 1101.67  4394.2 1099.93
  4465.5 1098.37  4491.9 1096.77  4557.2 1094.52  4595.8 1094.47  4600.9 1093.83
  4628.4 1095.48  4652.8 1095.86  4849.8 1093.41  4939.8 1089.88  4979.8 1086.22
  4997.3 1083.89  4997.7 1083.39  5002.0 1083.39  5002.4 1083.89  5019.8 1083.99
  5039.8 1087.07  5059.8 1088.48  5139.9 1089.92  5239.9 1088.75  5299.9 1089.71
  5389.9 1092.39  5509.0 1097.86  5514.0 1097.43  5560.0 1099.23  5612.8 1099.98
#Mann=3,-1,0
  4126.5    0.05       0  4997.3    0.05       0  5002.4    0.05       0
Bank Sta=4997.3,5002.4
Exp/Cntr=0.3,0.1

Type RM Length L Ch R = 1,1813,533,533,533
BEGIN DESCRIPTION:
LITTLE LLANO 043 2.0
END DESCRIPTION:
XS GIS Cut Line= 3
      2821743.47     10259176.97      2821483.68     10258233.27
      2821205.69     10258003.12
#Sta/Elev= 30
  4260.2 1109.36  4309.6 1108.20  4383.6 1104.63  4423.2 1103.78  4645.1 1095.02
  4658.3 1095.11  4684.7 1093.49  4689.9 1093.88  4719.1 1092.60  4724.3 1092.94
  4855.4 1089.18  4896.9 1087.38  4938.4 1083.90  4985.8 1081.59  4991.0 1082.05
  4998.0 1081.26  4998.4 1080.76  5002.8 1080.76  5003.2 1081.26  5011.0 1082.52
  5020.2 1086.75  5025.4 1086.93  5156.2 1086.96  5212.9 1088.78  5329.6 1095.64
  5372.6 1096.31  5401.3 1095.50  5479.4 1095.93  5543.3 1097.56  5599.9 1100.02
#Mann=3,-1,0
  4260.2    0.05       0  4998.0    0.03       0  5003.2    0.05       0
Bank Sta=4998,5003.2
Exp/Cntr=0.3,0.1

Type RM Length L Ch R = 1,1280,469,469,469
BEGIN DESCRIPTION:
Mapping XS 0b6d3d0a
END DESCRIPTION:
XS GIS Cut Line= 3
      2822197.27     10258601.10      2822067.07     10258384.09
      2821752.39     10258134.52
#Sta/Elev= 30
  4739.9 1099.05  4748.0 1098.95  4775.3 1101.04  4790.8 1100.04  4827.7 1099.79
  4854.9 1097.48  4877.5 1093.98  4886.0 1091.84  4923.0 1086.94  4942.1 1085.68
  4981.3 1083.13  4987.1 1082.12  4990.6 1079.04  4999.3 1078.57  4999.7 1078.07
  5004.5 1078.57  5022.7 1081.21  5045.1 1082.01  5058.6 1083.46  5101.2 1086.03
  5122.4 1086.60  5130.0 1087.51  5194.1 1089.83  5200.5 1091.07  5229.4 1090.49
  5264.6 1091.60  5287.1 1091.06  5293.5 1091.88  5307.9 1091.16  5394.6 1092.96
#Mann=4,-1,0
  4739.9    0.12       0  4942.1    0.05       0  4999.3    0.05       0
  5004.5    0.05       0
Bank Sta=4999.3,5004.5
Exp/Cntr=0.3,0.1

Type RM Length L Ch R = 1,811,627,627,627
BEGIN DESCRIPTION:
Mapping XS 511bbf6b
END DESCRIPTION:
XS GIS Cut Line= 4
      2822285.11     10258473.86      2822389.29     10258286.32
      2822326.79     10257885.28      2822066.40     10257328.04
#Sta/Elev= 30
  4533.5 1094.74  4586.0 1094.50  4607.7 1093.02  4710.7 1088.98  4726.7 1089.25
  4740.3 1087.34  4761.4 1087.45  4791.8 1085.65  4812.0 1086.13  4822.1 1087.87
  4842.4 1084.80  4862.6 1084.51  4873.3 1082.45  4963.8 1078.12  4984.1 1077.87
  4996.3 1076.10  4996.8 1075.60  5001.7 1076.10  5004.3 1078.17  5014.4 1080.89
  5034.7 1081.22  5061.8 1080.15  5105.5 1080.97  5135.9 1082.88  5157.9 1082.87
  5233.6 1086.08  5267.5 1088.94  5638.6 1096.32  5707.2 1099.17  5769.0 1103.74
#Mann=3,-1,0
  4533.5    0.05       0  4996.3    0.03       0  5001.7    0.05       0
Bank Sta=4996.3,5001.7
Exp/Cntr=0.3,0.1

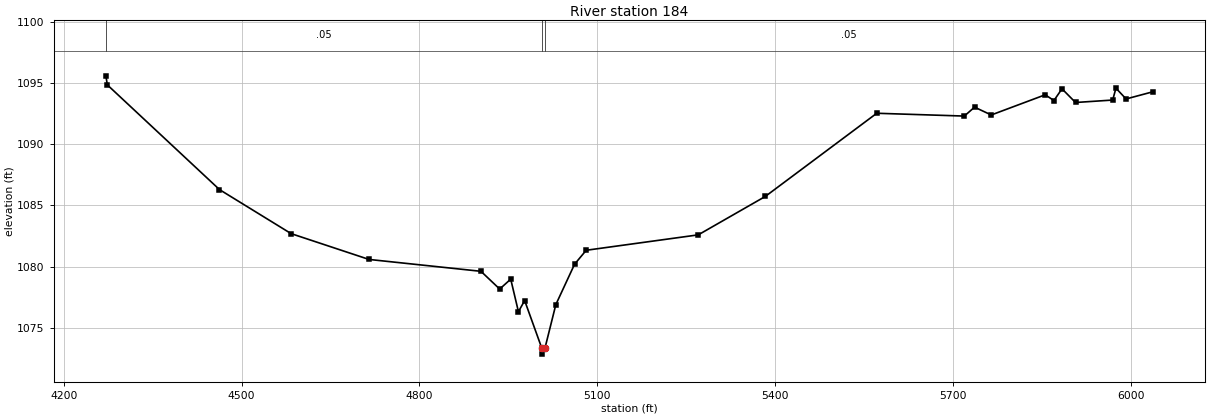
Type RM Length L Ch R = 1,184,0,0,0
BEGIN DESCRIPTION:
LITTLE LLANO 043 1.0
END DESCRIPTION:
XS GIS Cut Line= 4
      2822269.21     10258569.17      2822832.00     10258380.07
      2822955.68     10258003.11      2822623.69     10257301.99
#Sta/Elev= 30
  4271.1 1095.59  4273.5 1094.85  4462.7 1086.29  4583.5 1082.69  4714.9 1080.58
  4903.7 1079.61  4935.3 1078.16  4953.9 1078.97  4966.9 1076.31  4977.4 1077.22
  5006.2 1073.34  5006.7 1072.84  5011.7 1073.34  5030.0 1076.89  5061.6 1080.19
  5081.2 1081.33  5270.2 1082.59  5383.3 1085.73  5571.3 1092.53  5719.0 1092.30
  5736.2 1093.03  5764.4 1092.39  5855.4 1094.04  5870.1 1093.57  5883.7 1094.53
  5906.5 1093.41  5969.2 1093.61  5974.7 1094.58  5991.8 1093.70  6037.3 1094.29
#Mann=3,-1,0
  4271.1    0.05       0  5006.2    0.05       0  5011.7    0.05       0
Bank Sta=5006.2,5011.7
Exp/Cntr=0.3,0.1

Chan Stop Cuts=-1