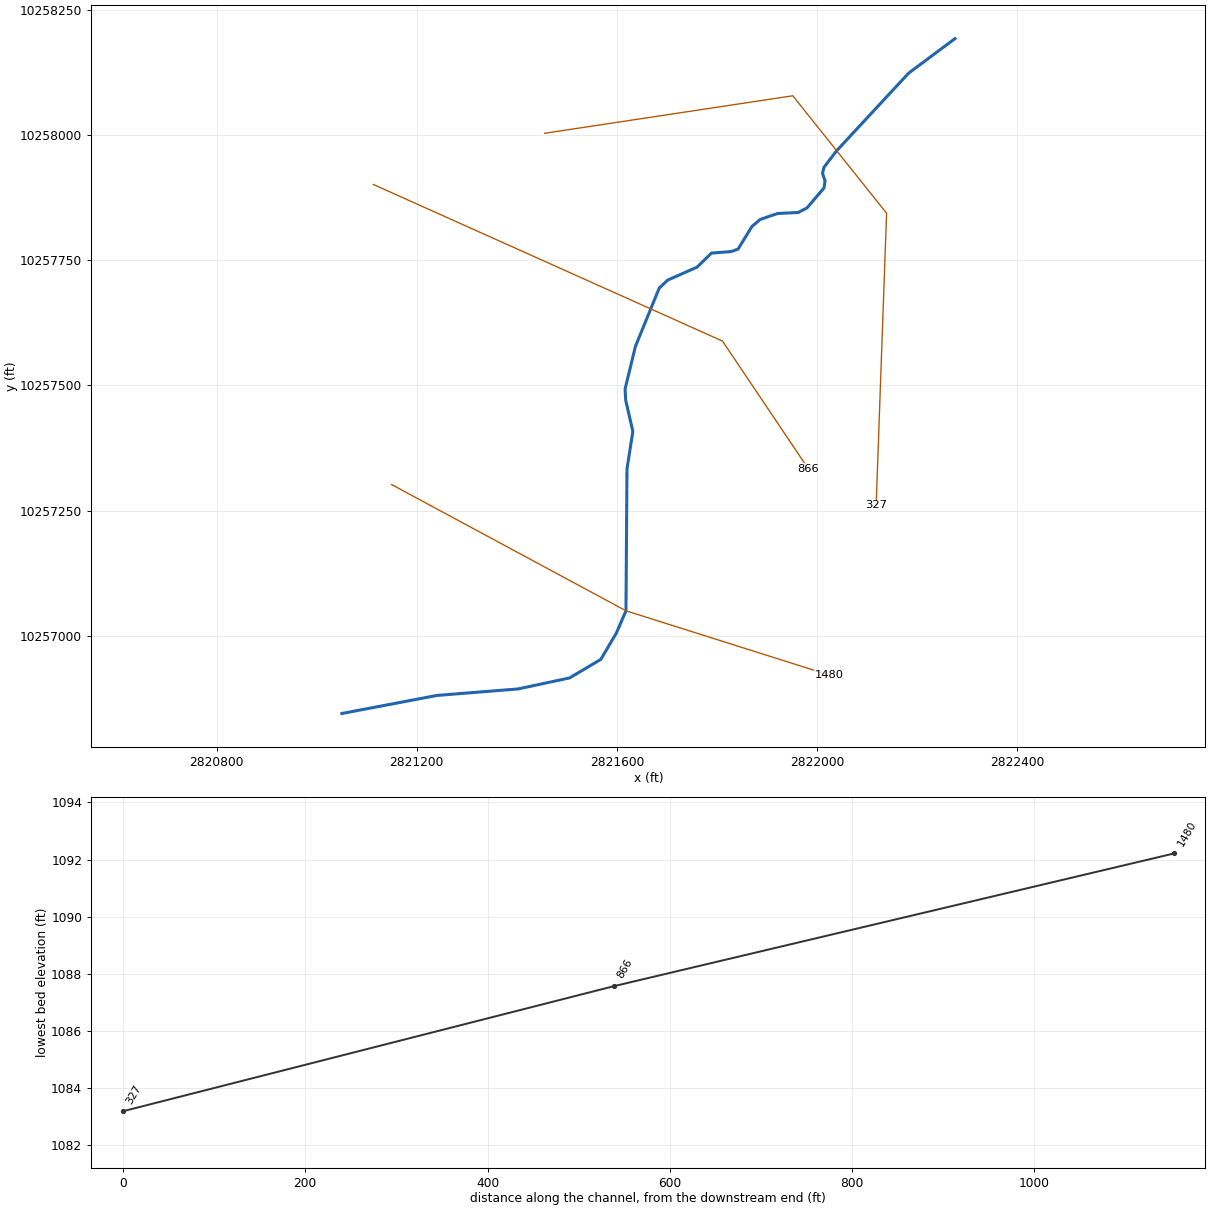
--- LITTLE LLANO 044.prj (project) ---

Proj Title=LITTLE LLANO 044 Base Level Engineering
Current Plan=p01
Default Exp/Contr=0.3,0.1
English Units
Geom File=g01
Flow File=f01
Plan File=p01
BEGIN DESCRIPTION:
LITTLE LLANO 044
END DESCRIPTION:

--- LITTLE LLANO 044.p01 (plan) ---

Plan Title=Multiple Run
Short Identifier=Multiple
Geom File=g01
Flow File=f01
Subcritical Flow
K Sum by GR= 0
Std Step Tol= 0.01
Critical Tol= 0.01
Num of Std Step Trials= 20
Max Error Tol= 0.3
Flow Tol Ratio= 0.001
Split Flow NTrial= 30
Split Flow Tol= 0.02
Split Flow Ratio= 0.02
Log Output Level= 0
Friction Slope Method= 1
Unsteady Friction Slope Method= 2
Unsteady Bridges Friction Slope Method= 1
Parabolic Critical Depth
Global Vel Dist=  1 , 1 , 1
Global Log Level= 0
CheckData=True
Encroach Param= -1, 0, 0, 0
BEGIN DESCRIPTION:
Multiple Run
END DESCRIPTION:

--- LITTLE LLANO 044.f01 (steady flow) ---

Flow Title=Multiple
Number of Profiles=7
Profile Names=10-year,25-year,50-year,1pct_min,100-year,1pct_plu,500-year
River Rch & RM= LITTLE LLANO 044,Reach-1,1480
      74     106     117      94     129     179     175
Boundary for River Rch & Prof#=LITTLE LLANO 044,Reach-1,1
Up Type=0
Dn Type=3
Dn Slope=0.005
Boundary for River Rch & Prof#=LITTLE LLANO 044,Reach-1,2
Up Type=0
Dn Type=3
Dn Slope=0.005
Boundary for River Rch & Prof#=LITTLE LLANO 044,Reach-1,3
Up Type=0
Dn Type=3
Dn Slope=0.005
Boundary for River Rch & Prof#=LITTLE LLANO 044,Reach-1,4
Up Type=0
Dn Type=3
Dn Slope=0.005
Boundary for River Rch & Prof#=LITTLE LLANO 044,Reach-1,5
Up Type=0
Dn Type=3
Dn Slope=0.005
Boundary for River Rch & Prof#=LITTLE LLANO 044,Reach-1,6
Up Type=0
Dn Type=3
Dn Slope=0.005
Boundary for River Rch & Prof#=LITTLE LLANO 044,Reach-1,7
Up Type=0
Dn Type=3
Dn Slope=0.005

--- LITTLE LLANO 044.g01 (geometry) ---

Geom Title=Existing Conditions

River Reach=LITTLE LLANO 044,Reach-1
Reach XY= 30
      2821050.25     10256845.00      2821240.00     10256881.00
      2821402.50     10256894.00      2821505.50     10256916.00
      2821568.00     10256953.00      2821599.25     10257006.00
      2821618.25     10257050.00      2821620.25     10257333.00
      2821632.00     10257408.00      2821617.75     10257470.00
      2821616.50     10257493.00      2821637.25     10257578.00
      2821684.75     10257694.00      2821701.50     10257710.00
      2821760.50     10257736.00      2821789.25     10257764.00
      2821828.50     10257767.00      2821842.50     10257772.00
      2821870.00     10257817.00      2821886.50     10257831.00
      2821921.25     10257843.00      2821962.50     10257845.00
      2821980.00     10257854.00      2822014.25     10257894.00
      2822016.25     10257908.00      2822011.25     10257923.00
      2822014.00     10257935.00      2822039.25     10257968.00
      2822183.25     10258123.00      2822276.00     10258192.00

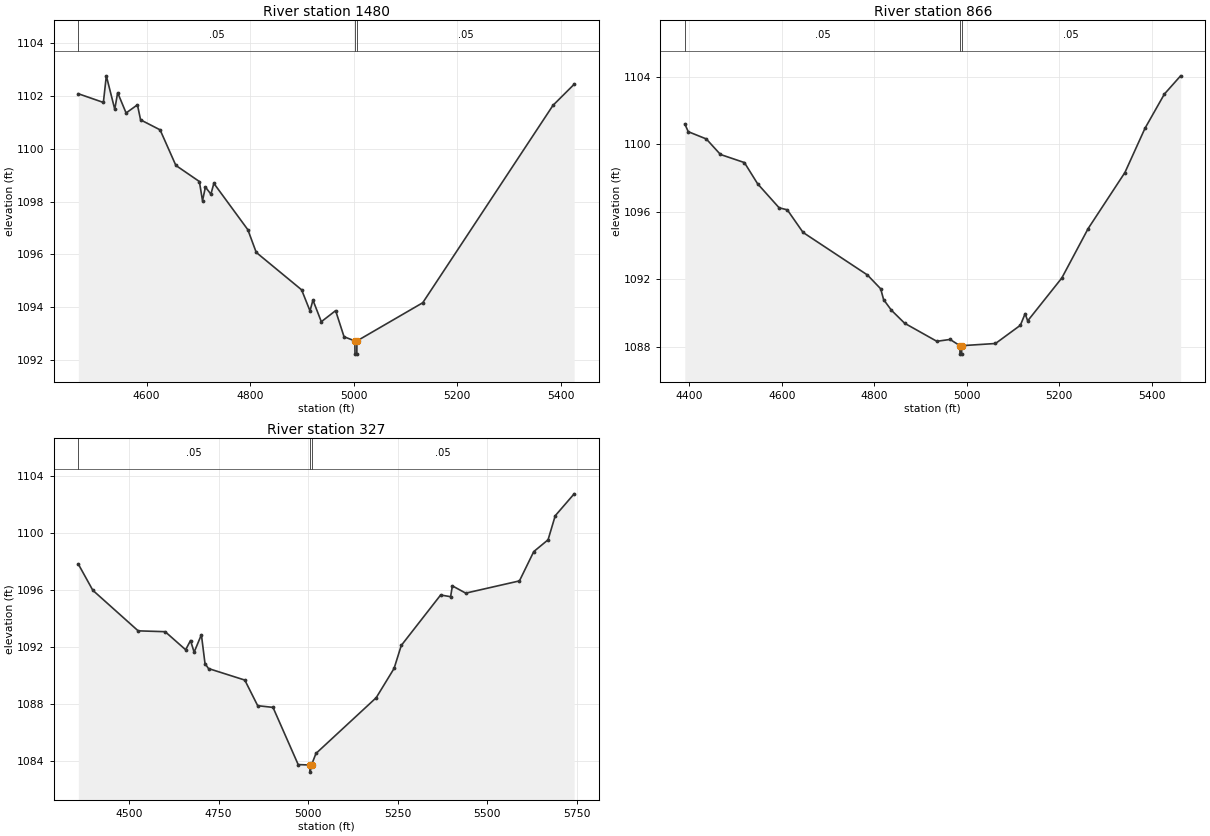
Type RM Length L Ch R = 1,1480,614,614,614
BEGIN DESCRIPTION:
LITTLE LLANO 044 3.0
END DESCRIPTION:
XS GIS Cut Line= 3
      2821149.70     10257301.95      2821618.25     10257050.00
      2822024.69     10256921.74
#Sta/Elev= 30
  4468.0 1102.09  4516.4 1101.76  4522.1 1102.77  4538.4 1101.50  4544.0 1102.13
  4560.3 1101.36  4582.2 1101.67  4588.3 1101.10  4626.0 1100.72  4656.5 1099.37
  4701.9 1098.76  4708.0 1098.03  4713.6 1098.55  4724.2 1098.28  4729.9 1098.69
  4795.6 1096.93  4811.8 1096.07  4899.5 1094.65  4915.7 1093.85  4921.4 1094.26
  4937.6 1093.44  4965.2 1093.86  4981.5 1092.87  5002.4 1092.71  5002.7 1092.21
  5006.2 1092.21  5006.4 1092.71  5133.6 1094.16  5385.3 1101.65  5426.2 1102.45
#Mann=3,-1,0
  4468.0    0.05       0  5002.4    0.03       0  5006.4    0.05       0
Bank Sta=5002.4,5006.4
Exp/Cntr=0.3,0.1

Type RM Length L Ch R = 1,866,539,539,539
BEGIN DESCRIPTION:
LITTLE LLANO 044 2.0
END DESCRIPTION:
XS GIS Cut Line= 3
      2821113.25     10257900.91      2821811.17     10257588.40
      2821983.06     10257333.18
#Sta/Elev= 30
  4390.1 1101.21  4397.6 1100.75  4436.6 1100.32  4467.2 1099.40  4519.0 1098.92
  4547.7 1097.66  4594.1 1096.24  4611.8 1096.12  4645.9 1094.78  4785.1 1092.26
  4813.8 1091.44  4820.1 1090.80  4837.0 1090.17  4865.6 1089.40  4935.2 1088.33
  4963.9 1088.44  4985.1 1088.07  4985.3 1087.57  4988.8 1087.57  4989.1 1088.07
  5062.1 1088.20  5115.9 1089.28  5126.2 1089.97  5131.7 1089.54  5205.5 1092.08
  5262.5 1095.01  5342.0 1098.33  5385.4 1100.95  5427.4 1102.98  5462.5 1104.06
#Mann=3,-1,0
  4390.1    0.05       0  4985.1    0.05       0  4989.1    0.05       0
Bank Sta=4985.1,4989.1
Exp/Cntr=0.3,0.1

Type RM Length L Ch R = 1,327,0,0,0
BEGIN DESCRIPTION:
LITTLE LLANO 044 1.0
END DESCRIPTION:
XS GIS Cut Line= 4
      2821455.68     10258003.11      2821951.79     10258077.99
      2822139.29     10257843.61      2822118.46     10257260.26
#Sta/Elev= 30
  4357.8 1097.81  4398.3 1095.97  4525.0 1093.12  4600.5 1093.06  4657.7 1091.79
  4671.3 1092.44  4681.4 1091.62  4701.7 1092.85  4711.8 1090.82  4721.6 1090.47
  4823.0 1089.66  4859.0 1087.86  4901.8 1087.74  4972.2 1083.72  5005.4 1083.69
  5005.7 1083.19  5009.4 1083.69  5021.8 1084.50  5190.2 1088.42  5240.2 1090.48
  5260.2 1092.09  5370.3 1095.64  5398.1 1095.52  5403.1 1096.28  5440.4 1095.77
  5590.5 1096.63  5630.5 1098.69  5670.5 1099.52  5690.5 1101.21  5743.4 1102.75
#Mann=3,-1,0
  4357.8    0.05       0  5005.4    0.03       0  5009.4    0.05       0
Bank Sta=5005.4,5009.4
Exp/Cntr=0.3,0.1

Chan Stop Cuts=-1