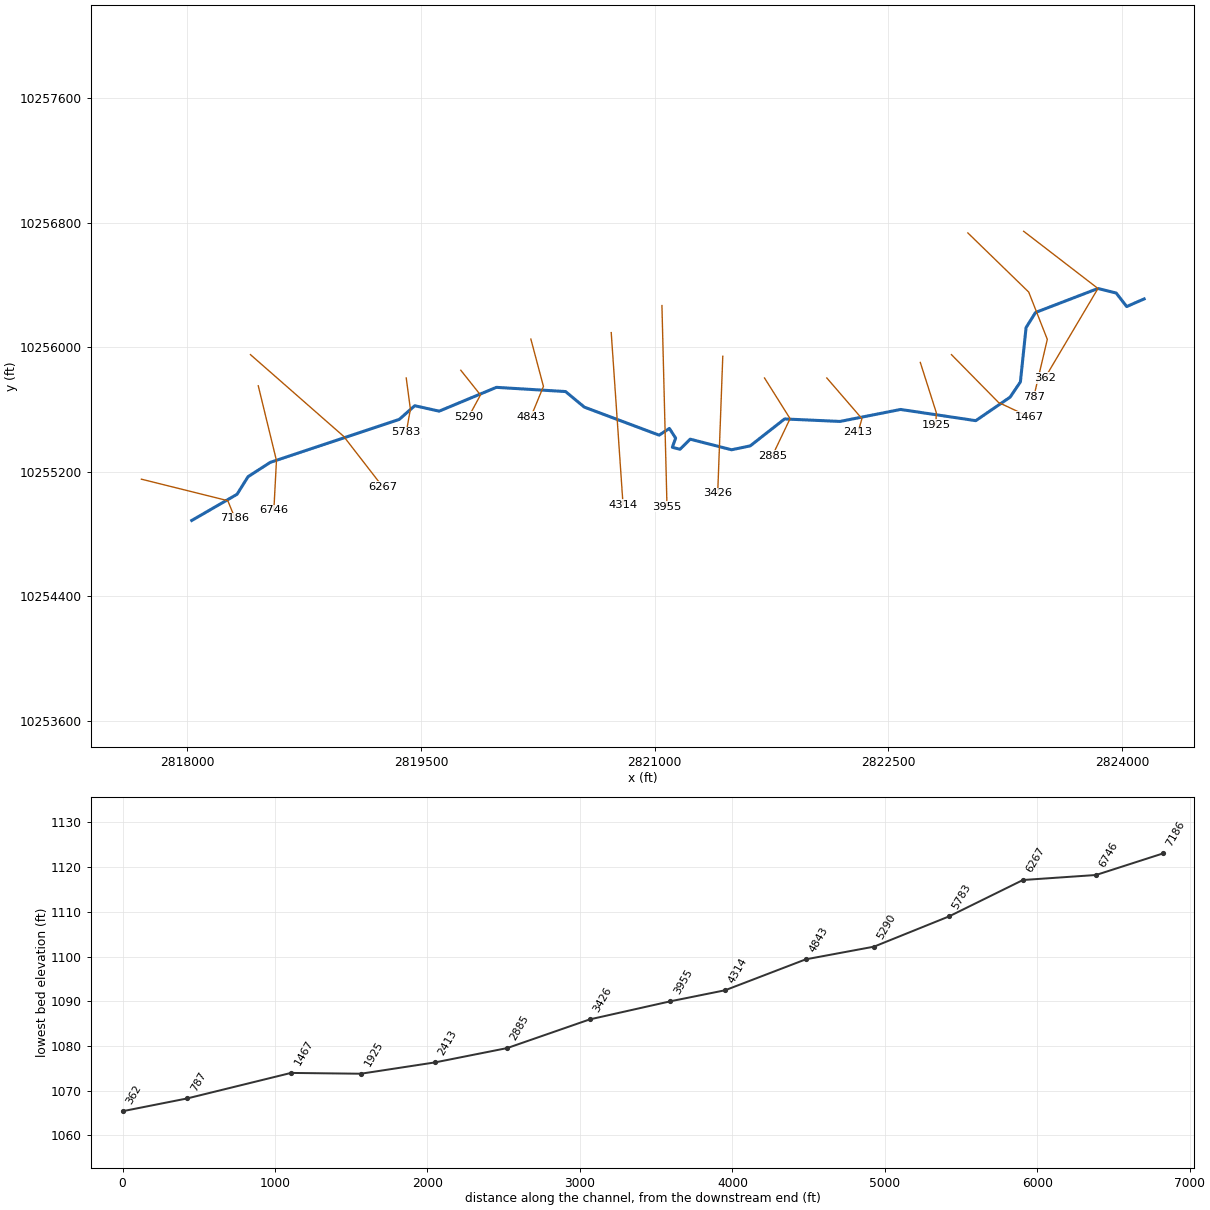
--- LITTLE LLANO 045.prj (project) ---

Proj Title=LITTLE LLANO 045 Base Level Engineering
Current Plan=p01
Default Exp/Contr=0.3,0.1
English Units
Geom File=g01
Flow File=f01
Plan File=p01
BEGIN DESCRIPTION:
LITTLE LLANO 045
END DESCRIPTION:

--- LITTLE LLANO 045.p01 (plan) ---

Plan Title=Multiple Run
Short Identifier=Multiple
Geom File=g01
Flow File=f01
Subcritical Flow
K Sum by GR= 0
Std Step Tol= 0.01
Critical Tol= 0.01
Num of Std Step Trials= 20
Max Error Tol= 0.3
Flow Tol Ratio= 0.001
Split Flow NTrial= 30
Split Flow Tol= 0.02
Split Flow Ratio= 0.02
Log Output Level= 0
Friction Slope Method= 1
Unsteady Friction Slope Method= 2
Unsteady Bridges Friction Slope Method= 1
Parabolic Critical Depth
Global Vel Dist=  1 , 1 , 1
Global Log Level= 0
CheckData=True
Encroach Param= -1, 0, 0, 0
BEGIN DESCRIPTION:
Multiple Run
END DESCRIPTION:

--- LITTLE LLANO 045.f01 (steady flow) ---

Flow Title=Multiple
Number of Profiles=7
Profile Names=10-year,25-year,50-year,1pct_min,100-year,1pct_plu,500-year
River Rch & RM= LITTLE LLANO 045,Reach-1,7186
     320     511     584     422     761    1373    1039
Boundary for River Rch & Prof#=LITTLE LLANO 045,Reach-1,1
Up Type=0
Dn Type=3
Dn Slope=0.005
Boundary for River Rch & Prof#=LITTLE LLANO 045,Reach-1,2
Up Type=0
Dn Type=3
Dn Slope=0.005
Boundary for River Rch & Prof#=LITTLE LLANO 045,Reach-1,3
Up Type=0
Dn Type=3
Dn Slope=0.005
Boundary for River Rch & Prof#=LITTLE LLANO 045,Reach-1,4
Up Type=0
Dn Type=3
Dn Slope=0.005
Boundary for River Rch & Prof#=LITTLE LLANO 045,Reach-1,5
Up Type=0
Dn Type=3
Dn Slope=0.005
Boundary for River Rch & Prof#=LITTLE LLANO 045,Reach-1,6
Up Type=0
Dn Type=3
Dn Slope=0.005
Boundary for River Rch & Prof#=LITTLE LLANO 045,Reach-1,7
Up Type=0
Dn Type=3
Dn Slope=0.005

--- LITTLE LLANO 045.g01 (geometry) ---

Geom Title=Existing Conditions

River Reach=LITTLE LLANO 045,Reach-1
Reach XY= 30
      2818028.75     10254888.00      2818319.50     10255056.00
      2818390.00     10255169.00      2818532.50     10255261.00
      2819360.50     10255537.00      2819460.50     10255625.00
      2819616.75     10255590.00      2819984.50     10255743.00
      2820428.25     10255716.00      2820549.00     10255616.00
      2821029.00     10255436.00      2821095.00     10255479.00
      2821135.00     10255417.00      2821114.00     10255358.00
      2821162.75     10255345.00      2821228.75     10255410.00
      2821494.25     10255342.00      2821614.00     10255367.00
      2821834.50     10255540.00      2822190.25     10255524.00
      2822579.25     10255601.00      2823061.75     10255529.00
      2823282.25     10255680.00      2823348.25     10255778.00
      2823384.75     10256127.00      2823445.50     10256224.00
      2823846.25     10256378.00      2823963.00     10256349.00
      2824030.50     10256262.00      2824142.75     10256311.00

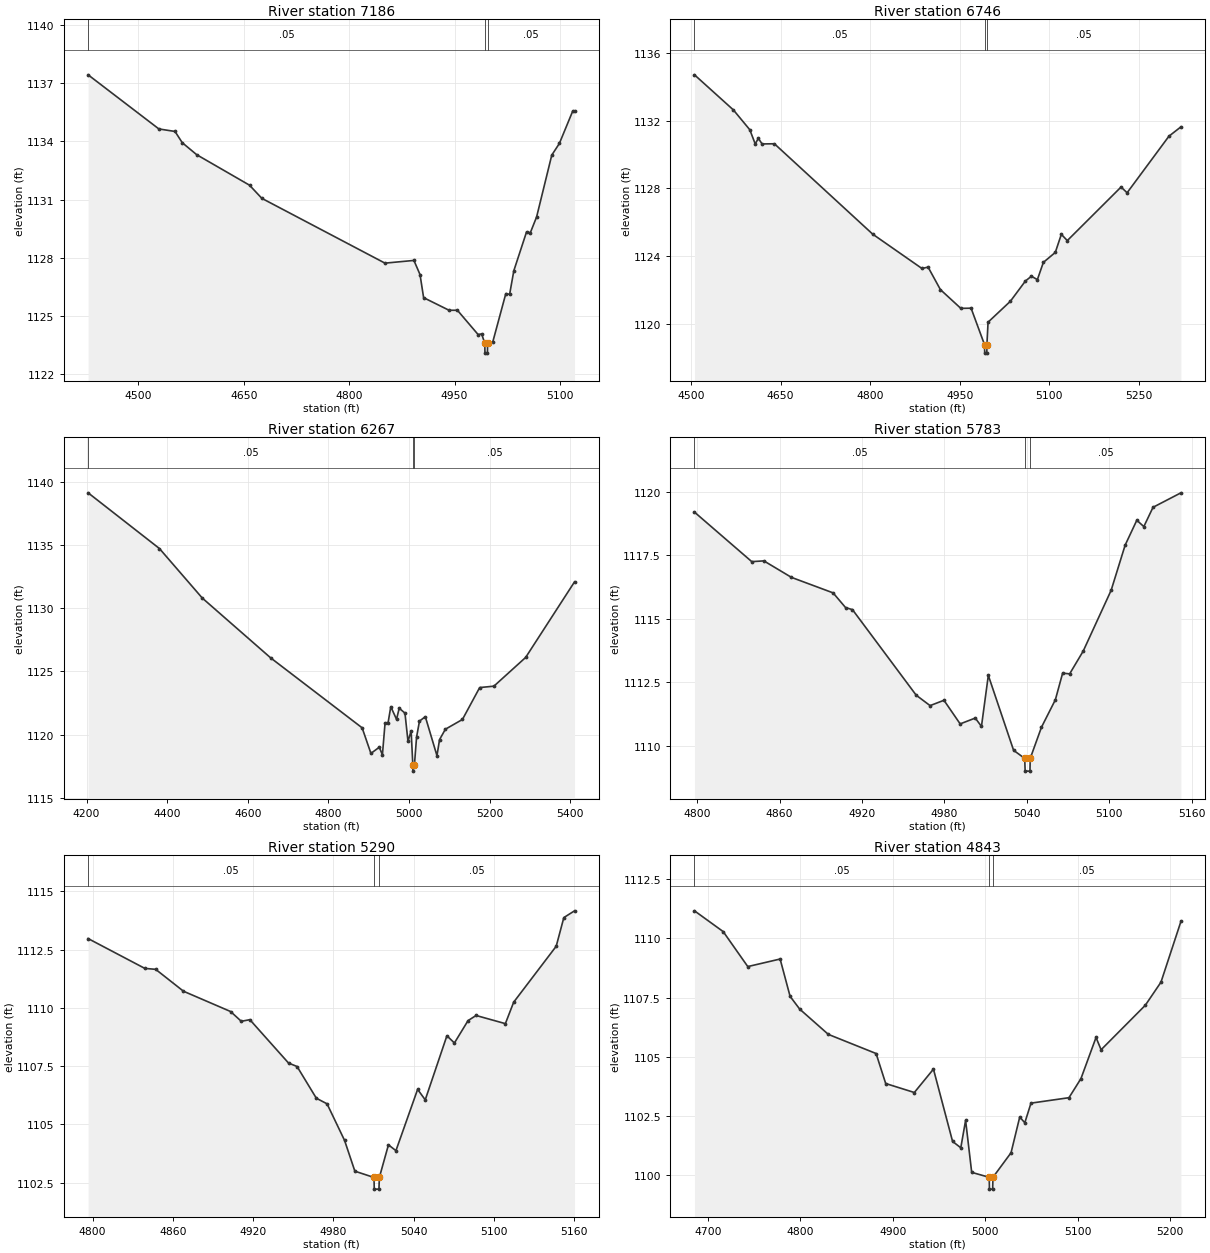
Type RM Length L Ch R = 1,7186,440,440,440
BEGIN DESCRIPTION:
LITTLE LLANO 045 14.0
END DESCRIPTION:
XS GIS Cut Line= 3
      2817705.69     10255153.11      2818260.25     10255015.00
      2818305.70     10254903.08
#Sta/Elev= 30
  4428.5 1137.43  4529.2 1134.64  4552.2 1134.51  4562.5 1133.93  4583.1 1133.31
  4658.2 1131.74  4675.8 1131.06  4851.0 1127.72  4892.2 1127.86  4900.9 1127.13
  4906.0 1125.94  4942.2 1125.29  4954.1 1125.29  4983.5 1124.04  4988.6 1124.07
  4993.1 1123.58  4993.3 1123.08  4996.8 1123.08  4997.1 1123.58  5004.3 1123.64
  5023.0 1126.15  5028.4 1126.11  5034.4 1127.33  5052.5 1129.33  5057.9 1129.29
  5066.8 1130.10  5088.4 1133.29  5099.2 1133.89  5118.1 1135.55  5120.8 1135.55
#Mann=3,-1,0
  4428.5    0.05       0  4993.1    0.03       0  4997.1    0.05       0
Bank Sta=4993.1,4997.1
Exp/Cntr=0.3,0.1

Type RM Length L Ch R = 1,6746,479,479,479
BEGIN DESCRIPTION:
LITTLE LLANO 045 13.0
END DESCRIPTION:
XS GIS Cut Line= 3
      2818455.69     10255753.09      2818572.50     10255273.00
      2818555.69     10254953.14
#Sta/Elev= 30
  4505.9 1134.72  4571.1 1132.64  4598.5 1131.47  4607.6 1130.63  4612.8 1130.96
  4619.1 1130.63  4639.7 1130.64  4804.3 1125.29  4886.7 1123.26  4897.0 1123.34
  4917.6 1122.01  4951.8 1120.90  4969.0 1120.91  4991.5 1118.75  4991.8 1118.25
  4995.3 1118.25  4995.5 1118.75  4997.4 1120.08  5034.8 1121.32  5060.0 1122.52
  5070.0 1122.80  5080.0 1122.60  5090.0 1123.62  5110.0 1124.21  5120.1 1125.28
  5130.1 1124.91  5220.1 1128.08  5230.2 1127.74  5300.3 1131.09  5320.3 1131.64
#Mann=3,-1,0
  4505.9    0.05       0  4991.5    0.05       0  4995.5    0.05       0
Bank Sta=4991.5,4995.5
Exp/Cntr=0.3,0.1

Type RM Length L Ch R = 1,6267,484,484,484
BEGIN DESCRIPTION:
LITTLE LLANO 045 12.0
END DESCRIPTION:
XS GIS Cut Line= 3
      2818405.65     10255953.14      2819004.25     10255428.00
      2819255.67     10255103.13
#Sta/Elev= 30
  4203.7 1139.11  4380.7 1134.71  4487.0 1130.80  4656.9 1126.07  4883.7 1120.55
  4905.5 1118.53  4926.4 1119.02  4934.0 1118.41  4940.6 1120.93  4948.2 1120.97
  4954.8 1122.22  4969.1 1121.22  4975.7 1122.10  4990.0 1121.71  4997.5 1119.48
  5005.3 1120.30  5009.5 1117.63  5009.8 1117.13  5013.5 1117.63  5018.8 1119.82
  5026.0 1121.08  5040.5 1121.43  5069.4 1118.35  5075.8 1119.62  5090.3 1120.44
  5132.6 1121.21  5175.4 1123.73  5210.7 1123.84  5289.5 1126.11  5410.8 1132.08
#Mann=3,-1,0
  4203.7    0.05       0  5009.5    0.05       0  5013.5    0.05       0
Bank Sta=5009.5,5013.5
Exp/Cntr=0.3,0.1

Type RM Length L Ch R = 1,5783,493,493,493
BEGIN DESCRIPTION:
LITTLE LLANO 045 11.0
END DESCRIPTION:
XS GIS Cut Line= 3
      2819405.68     10255803.14      2819432.25     10255603.00
      2819405.69     10255453.14
#Sta/Elev= 30
  4798.1 1119.20  4839.8 1117.25  4848.6 1117.28  4868.7 1116.63  4899.0 1116.02
  4908.1 1115.44  4913.1 1115.36  4959.5 1111.99  4969.6 1111.58  4979.7 1111.79
  4991.5 1110.86  5002.5 1111.09  5007.0 1110.76  5012.0 1112.77  5030.4 1109.82
  5038.5 1109.50  5038.8 1109.00  5042.3 1109.00  5042.5 1109.50  5050.7 1110.73
  5060.8 1111.81  5066.1 1112.86  5071.2 1112.83  5081.1 1113.73  5101.4 1116.12
  5111.6 1117.90  5120.1 1118.88  5125.2 1118.63  5131.9 1119.39  5152.2 1119.96
#Mann=3,-1,0
  4798.1    0.05       0  5038.5    0.05       0  5042.5    0.05       0
Bank Sta=5038.5,5042.5
Exp/Cntr=0.3,0.1

Type RM Length L Ch R = 1,5290,447,447,447
BEGIN DESCRIPTION:
LITTLE LLANO 045 10.0
END DESCRIPTION:
XS GIS Cut Line= 3
      2819755.69     10255853.10      2819882.25     10255694.00
      2819805.71     10255553.15
#Sta/Elev= 30
  4796.7 1112.97  4839.1 1111.69  4847.2 1111.65  4868.0 1110.71  4903.2 1109.84
  4911.2 1109.42  4917.6 1109.49  4946.5 1107.63  4952.9 1107.48  4967.3 1106.12
  4975.3 1105.88  4988.4 1104.31  4996.1 1102.99  5010.4 1102.72  5010.6 1102.22
  5014.1 1102.22  5014.4 1102.72  5021.2 1104.12  5026.8 1103.87  5043.0 1106.50
  5048.7 1106.05  5064.9 1108.80  5070.5 1108.49  5080.7 1109.45  5086.7 1109.67
  5108.6 1109.32  5114.8 1110.24  5146.6 1112.64  5152.3 1113.87  5160.3 1114.16
#Mann=3,-1,0
  4796.7    0.05       0  5010.4    0.05       0  5014.4    0.05       0
Bank Sta=5010.4,5014.4
Exp/Cntr=0.3,0.1

Type RM Length L Ch R = 1,4843,529,529,529
BEGIN DESCRIPTION:
LITTLE LLANO 045 9.0
END DESCRIPTION:
XS GIS Cut Line= 3
      2820205.68     10256053.14      2820286.50     10255749.00
      2820205.69     10255553.12
#Sta/Elev= 30
  4685.3 1111.17  4716.4 1110.29  4743.0 1108.81  4778.0 1109.13  4788.8 1107.55
  4799.2 1107.01  4830.2 1105.94  4881.9 1105.13  4892.3 1103.86  4923.3 1103.48
  4944.0 1104.47  4964.7 1101.41  4973.6 1101.14  4978.8 1102.30  4985.4 1100.10
  5004.4 1099.89  5004.6 1099.39  5008.1 1099.39  5008.4 1099.89  5028.0 1100.93
  5037.4 1102.44  5042.9 1102.20  5049.6 1103.03  5090.7 1103.26  5103.7 1104.07
  5120.0 1105.81  5125.5 1105.29  5173.3 1107.17  5190.3 1108.15  5211.9 1110.72
#Mann=3,-1,0
  4685.3    0.05       0  5004.4    0.05       0  5008.4    0.05       0
Bank Sta=5004.4,5008.4
Exp/Cntr=0.3,0.1

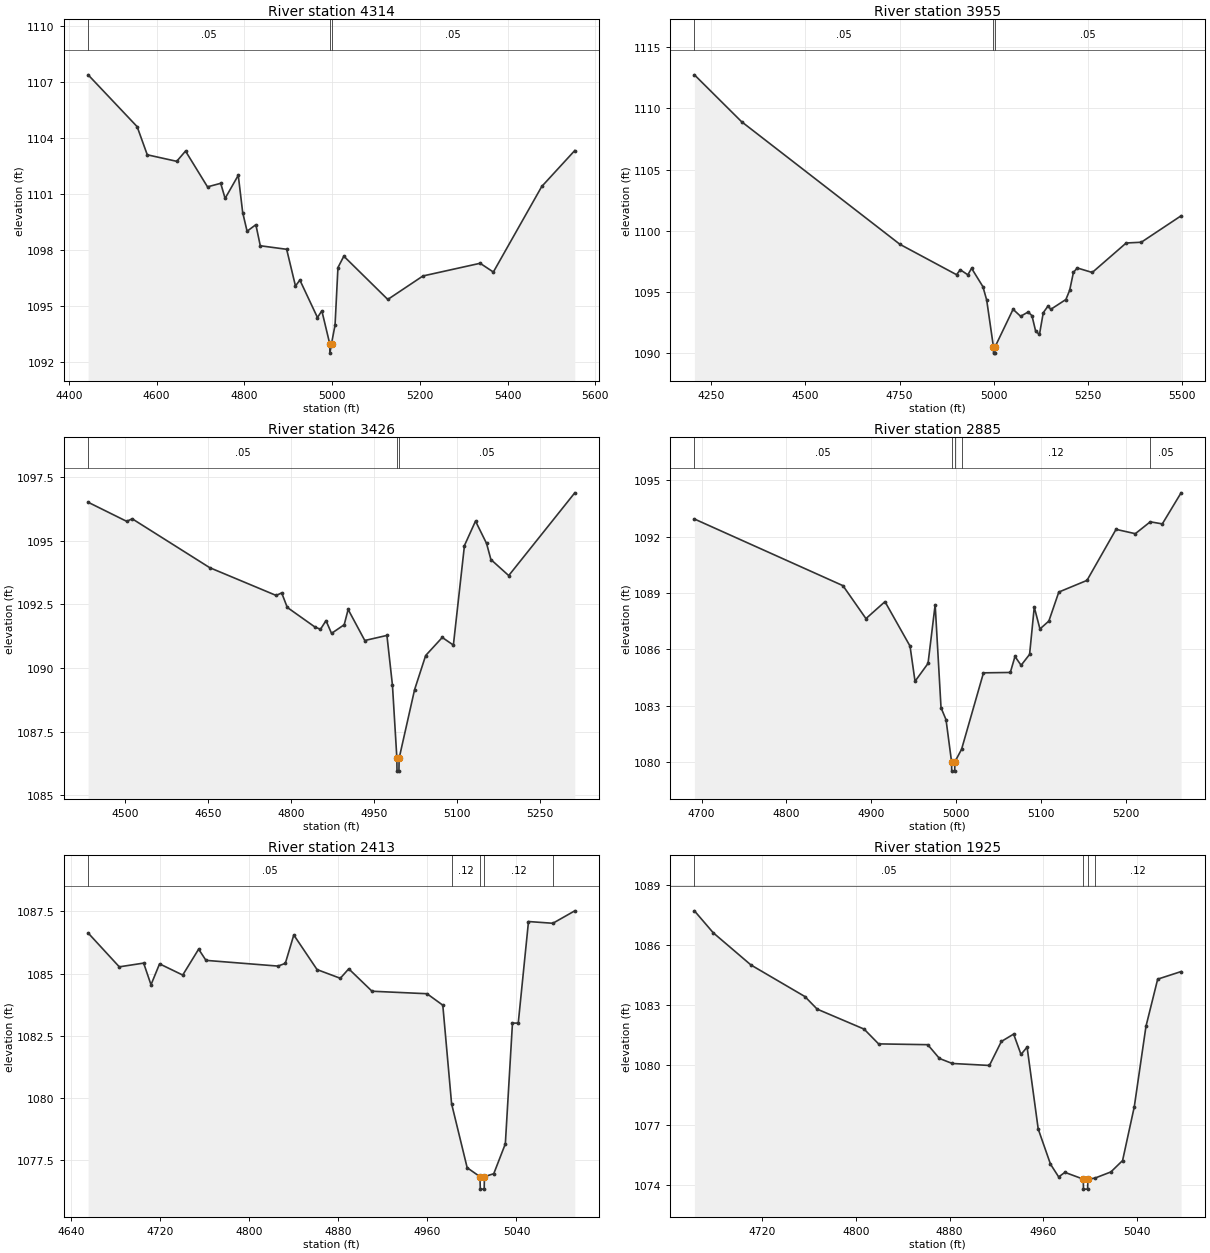
Type RM Length L Ch R = 1,4314,359,359,359
BEGIN DESCRIPTION:
Mapping XS f97ca319
END DESCRIPTION:
XS GIS Cut Line= 2
      2820721.59     10256094.56      2820797.53     10254987.96
#Sta/Elev= 30
  4444.1 1107.40  4555.8 1104.62  4578.9 1103.11  4646.0 1102.76  4666.1 1103.31
  4716.2 1101.39  4746.3 1101.58  4756.3 1100.77  4786.3 1102.01  4796.4 1100.01
  4806.4 1099.01  4826.4 1099.36  4836.5 1098.23  4896.6 1098.04  4916.7 1096.07
  4926.7 1096.39  4966.8 1094.38  4976.8 1094.74  4994.8 1092.97  4995.1 1092.47
  4998.8 1092.97  5006.9 1093.98  5013.5 1097.06  5026.9 1097.67  5127.1 1095.35
  5207.3 1096.61  5337.6 1097.29  5367.7 1096.82  5478.0 1101.41  5553.3 1103.34
#Mann=3,-1,0
  4444.1    0.05       0  4994.8    0.03       0  4998.8    0.05       0
Bank Sta=4994.8,4998.8
Exp/Cntr=0.3,0.1

Type RM Length L Ch R = 1,3955,529,529,529
BEGIN DESCRIPTION:
Mapping XS 81248311
END DESCRIPTION:
XS GIS Cut Line= 2
      2821047.11     10256268.18      2821079.64     10254977.59
#Sta/Elev= 30
  4205.6 1112.74  4330.7 1108.91  4750.8 1098.89  4900.9 1096.41  4910.9 1096.81
  4930.9 1096.40  4940.9 1096.93  4970.9 1095.43  4980.9 1094.34  4998.9 1090.50
  4999.2 1090.00  5002.7 1090.00  5002.9 1090.50  5050.9 1093.58  5070.9 1093.01
  5090.9 1093.36  5101.0 1093.06  5111.0 1091.77  5121.0 1091.54  5131.0 1093.30
  5143.6 1093.85  5151.0 1093.58  5191.0 1094.38  5201.0 1095.13  5211.0 1096.59
  5221.0 1096.96  5261.0 1096.59  5351.0 1099.00  5391.0 1099.06  5496.6 1101.22
#Mann=3,-1,0
  4205.6    0.05       0  4998.9    0.03       0  5002.9    0.05       0
Bank Sta=4998.9,5002.9
Exp/Cntr=0.3,0.1

Type RM Length L Ch R = 1,3426,541,541,541
BEGIN DESCRIPTION:
Mapping XS f0b60e81
END DESCRIPTION:
XS GIS Cut Line= 2
      2821437.73     10255942.72      2821405.18     10255063.82
#Sta/Elev= 30
  4432.9 1096.51  4502.6 1095.76  4512.6 1095.86  4652.7 1093.94  4772.7 1092.85
  4782.7 1092.95  4792.8 1092.38  4842.8 1091.61  4852.8 1091.52  4862.8 1091.86
  4872.8 1091.36  4895.7 1091.70  4902.8 1092.30  4932.9 1091.08  4972.9 1091.28
  4982.9 1089.32  4990.9 1086.45  4991.1 1085.95  4994.6 1085.95  4994.9 1086.45
  5022.9 1089.15  5042.9 1090.49  5072.9 1091.20  5093.0 1090.90  5113.0 1094.81
  5133.0 1095.77  5153.0 1094.89  5160.8 1094.26  5193.0 1093.63  5312.4 1096.88
#Mann=3,-1,0
  4432.9    0.05       0  4990.9    0.03       0  4994.9    0.05       0
Bank Sta=4990.9,4994.9
Exp/Cntr=0.3,0.1

Type RM Length L Ch R = 1,2885,472,472,472
BEGIN DESCRIPTION:
LITTLE LLANO 045 5.0
END DESCRIPTION:
XS GIS Cut Line= 3
      2821705.67     10255803.13      2821869.75     10255542.00
      2821755.69     10255303.13
#Sta/Elev= 30
  4691.6 1092.93  4866.5 1089.39  4893.6 1087.64  4916.0 1088.54  4945.5 1086.18
  4951.4 1084.31  4966.7 1085.26  4975.1 1088.38  4982.0 1082.91  4987.9 1082.27
  4994.4 1080.04  4994.6 1079.54  4998.1 1079.54  4998.4 1080.04  5006.2 1080.70
  5032.0 1084.76  5063.6 1084.78  5069.1 1085.63  5076.3 1085.16  5086.3 1085.74
  5091.8 1088.25  5098.5 1087.09  5109.0 1087.51  5120.7 1089.05  5153.9 1089.67
  5188.1 1092.38  5210.8 1092.15  5228.4 1092.78  5242.6 1092.67  5264.7 1094.32
#Mann=5,-1,0
  4691.6    0.05       0  4994.4    0.05       0  4998.4    0.05       0
  5006.2    0.12       0  5228.4    0.05       0
Bank Sta=4994.4,4998.4
Exp/Cntr=0.3,0.1

Type RM Length L Ch R = 1,2413,488,488,488
BEGIN DESCRIPTION:
LITTLE LLANO 045 4.0
END DESCRIPTION:
XS GIS Cut Line= 3
      2822105.68     10255803.12      2822331.00     10255542.00
      2822305.69     10255453.13
#Sta/Elev= 30
  4655.1 1086.63  4683.1 1085.27  4705.0 1085.42  4711.6 1084.55  4719.3 1085.39
  4740.1 1084.94  4754.4 1085.98  4761.0 1085.53  4825.7 1085.30  4832.3 1085.41
  4839.9 1086.55  4860.8 1085.16  4881.7 1084.81  4889.3 1085.19  4910.2 1084.29
  4959.6 1084.19  4973.8 1083.73  4981.7 1079.77  4995.7 1077.20  5007.2 1076.84
  5007.5 1076.34  5011.0 1076.34  5011.2 1076.84  5019.6 1076.96  5030.0 1078.16
  5036.4 1083.01  5041.6 1083.01  5050.8 1087.09  5072.7 1087.02  5092.4 1087.52
#Mann=5,-1,0
  4655.1    0.05       0  4981.7    0.12       0  5007.2    0.07       0
  5011.2    0.12       0  5072.7    0.05       0
Bank Sta=5007.2,5011.2
Exp/Cntr=0.3,0.1

Type RM Length L Ch R = 1,1925,458,458,458
BEGIN DESCRIPTION:
LITTLE LLANO 045 3.0
END DESCRIPTION:
XS GIS Cut Line= 3
      2822705.70     10255903.07      2822808.25     10255581.00
      2822805.69     10255503.14
#Sta/Elev= 30
  4662.0 1087.73  4678.1 1086.63  4710.3 1085.02  4756.4 1083.44  4766.9 1082.81
  4807.0 1081.81  4819.4 1081.07  4861.4 1081.03  4871.4 1080.34  4882.3 1080.09
  4914.1 1079.99  4924.3 1081.19  4934.8 1081.56  4941.1 1080.54  4946.3 1080.91
  4955.8 1076.81  4966.3 1075.05  4973.3 1074.41  4978.6 1074.64  4994.3 1074.30
  4994.5 1073.80  4998.0 1073.80  4998.3 1074.30  5004.2 1074.35  5017.9 1074.66
  5027.9 1075.23  5037.9 1077.92  5047.9 1081.95  5057.9 1084.31  5077.9 1084.69
#Mann=4,-1,0
  4662.0    0.05       0  4994.3    0.05       0  4998.3    0.05       0
  5004.2    0.12       0
Bank Sta=4994.3,4998.3
Exp/Cntr=0.3,0.1

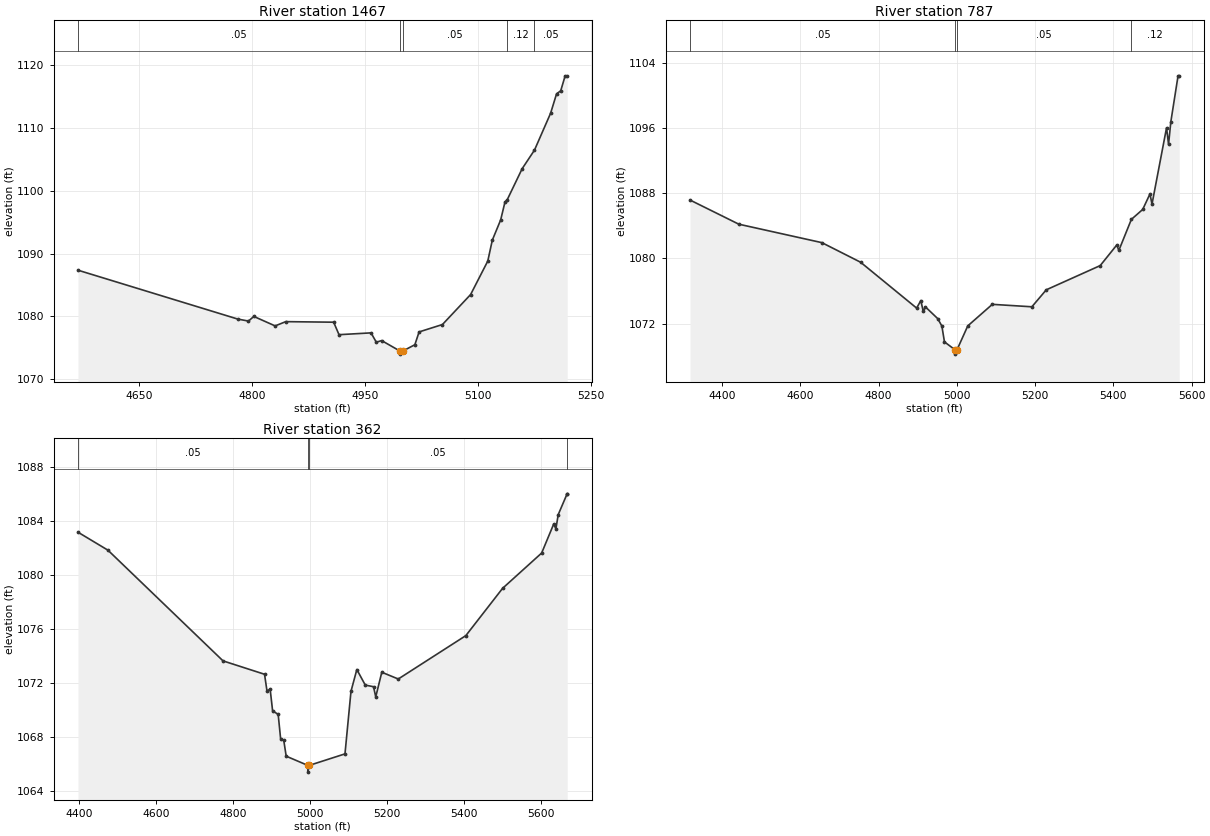
Type RM Length L Ch R = 1,1467,680,680,680
BEGIN DESCRIPTION:
LITTLE LLANO 045 2.0
END DESCRIPTION:
XS GIS Cut Line= 3
      2822905.66     10255953.13      2823207.75     10255646.00
      2823405.64     10255553.13
#Sta/Elev= 30
  4569.2 1087.36  4781.3 1079.57  4795.5 1079.25  4802.6 1079.99  4830.9 1078.48
  4845.0 1079.16  4908.6 1079.07  4915.7 1077.08  4958.2 1077.37  4965.2 1075.88
  4972.3 1076.14  4996.5 1074.48  4996.8 1073.98  5000.5 1074.48  5016.4 1075.48
  5022.0 1077.52  5053.0 1078.70  5090.4 1083.48  5113.2 1088.82  5119.2 1092.15
  5130.3 1095.38  5136.0 1098.22  5139.1 1098.62  5158.8 1103.54  5175.2 1106.51
  5196.6 1112.39  5204.5 1115.48  5210.0 1115.96  5215.9 1118.35  5218.6 1118.35
#Mann=5,-1,0
  4569.2    0.05       0  4996.5    0.05       0  5000.5    0.05       0
  5139.1    0.12       0  5175.2    0.05       0
Bank Sta=4996.5,5000.5
Exp/Cntr=0.3,0.1

Type RM Length L Ch R = 1,787,425,425,425
BEGIN DESCRIPTION:
Mapping XS 31d9a978
END DESCRIPTION:
XS GIS Cut Line= 4
      2823011.08     10256734.79      2823401.71     10256355.01
      2823521.06     10256051.19      2823434.27     10255682.31
#Sta/Elev= 30
  4318.1 1087.16  4442.8 1084.20  4655.0 1081.94  4754.0 1079.54  4897.2 1073.92
  4907.9 1074.84  4914.1 1073.51  4919.4 1074.08  4950.9 1072.64  4961.7 1071.72
  4968.3 1069.78  4996.1 1068.78  4996.3 1068.28  5000.1 1068.78  5027.9 1071.74
  5090.6 1074.38  5191.7 1074.08  5228.5 1076.16  5366.4 1079.13  5408.8 1081.66
  5413.9 1080.98  5446.0 1084.79  5475.0 1086.01  5493.5 1087.91  5498.7 1086.66
  5535.9 1096.02  5541.0 1093.99  5546.9 1096.77  5565.3 1102.38  5568.3 1102.38
#Mann=4,-1,0
  4318.1    0.05       0  4996.1    0.05       0  5000.1    0.05       0
  5446.0    0.12       0
Bank Sta=4996.1,5000.1
Exp/Cntr=0.3,0.1

Type RM Length L Ch R = 1,362,0,0,0
BEGIN DESCRIPTION:
LITTLE LLANO 045 1.0
END DESCRIPTION:
XS GIS Cut Line= 3
      2823369.16     10256745.63      2823846.25     10256378.00
      2823505.68     10255803.11
#Sta/Elev= 30
  4397.7 1083.16  4475.5 1081.83  4774.4 1073.64  4882.2 1072.65  4888.6 1071.40
  4896.7 1071.56  4903.1 1069.95  4917.6 1069.68  4923.9 1067.89  4932.1 1067.76
  4938.4 1066.59  4994.4 1065.91  4994.6 1065.41  4998.4 1065.91  5091.1 1066.76
  5106.7 1071.39  5121.9 1073.00  5143.8 1071.85  5165.2 1071.73  5171.0 1070.98
  5186.7 1072.80  5229.5 1072.30  5405.0 1075.51  5500.5 1079.01  5601.9 1081.62
  5633.1 1083.76  5638.9 1083.41  5644.9 1084.46  5668.0 1086.00  5668.2 1086.00
#Mann=4,-1,0
  4397.7    0.05       0  4994.4    0.05       0  4998.4    0.05       0
  5668.0    0.12       0
Bank Sta=4994.4,4998.4
Exp/Cntr=0.3,0.1

Chan Stop Cuts=-1