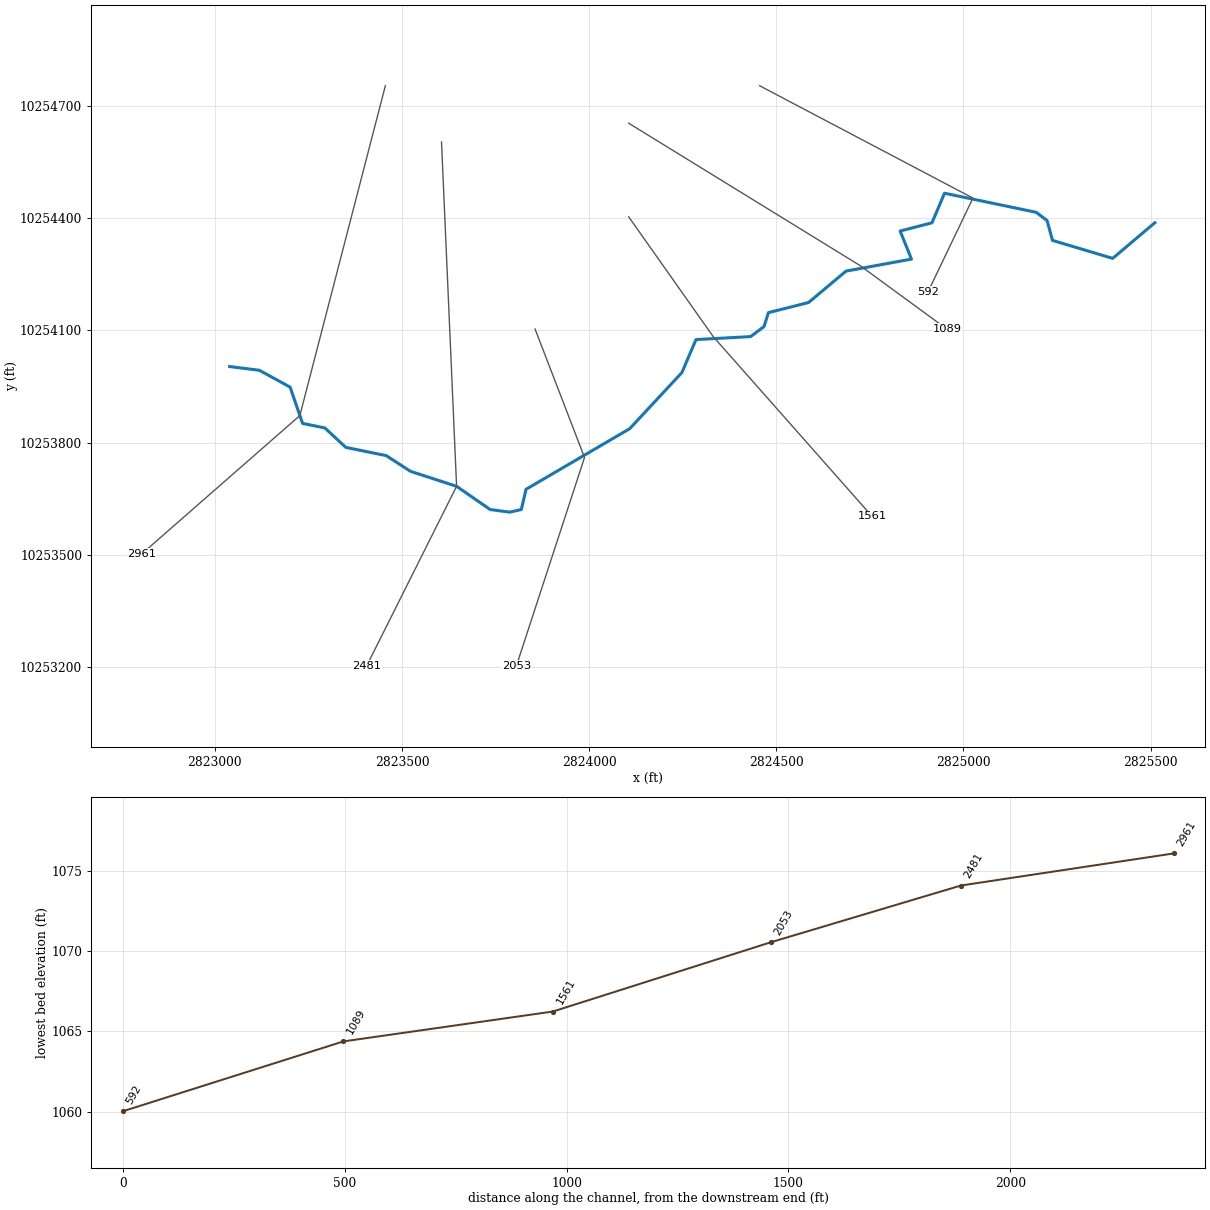
--- LITTLE LLANO 046.prj (project) ---

Proj Title=LITTLE LLANO 046 Base Level Engineering
Current Plan=p01
Default Exp/Contr=0.3,0.1
English Units
Geom File=g01
Flow File=f01
Plan File=p01
BEGIN DESCRIPTION:
LITTLE LLANO 046
END DESCRIPTION:

--- LITTLE LLANO 046.p01 (plan) ---

Plan Title=Multiple Run
Short Identifier=Multiple
Geom File=g01
Flow File=f01
Subcritical Flow
K Sum by GR= 0
Std Step Tol= 0.01
Critical Tol= 0.01
Num of Std Step Trials= 20
Max Error Tol= 0.3
Flow Tol Ratio= 0.001
Split Flow NTrial= 30
Split Flow Tol= 0.02
Split Flow Ratio= 0.02
Log Output Level= 0
Friction Slope Method= 1
Unsteady Friction Slope Method= 2
Unsteady Bridges Friction Slope Method= 1
Parabolic Critical Depth
Global Vel Dist=  1 , 1 , 1
Global Log Level= 0
CheckData=True
Encroach Param= -1, 0, 0, 0
BEGIN DESCRIPTION:
Multiple Run
END DESCRIPTION:

--- LITTLE LLANO 046.f01 (steady flow) ---

Flow Title=Multiple
Number of Profiles=7
Profile Names=10-year,25-year,50-year,1pct_min,100-year,1pct_plu,500-year
River Rch & RM= LITTLE LLANO 046,Reach-1,2961
     183     197     219     159     267     450     348
Boundary for River Rch & Prof#=LITTLE LLANO 046,Reach-1,1
Up Type=0
Dn Type=3
Dn Slope=0.005
Boundary for River Rch & Prof#=LITTLE LLANO 046,Reach-1,2
Up Type=0
Dn Type=3
Dn Slope=0.005
Boundary for River Rch & Prof#=LITTLE LLANO 046,Reach-1,3
Up Type=0
Dn Type=3
Dn Slope=0.005
Boundary for River Rch & Prof#=LITTLE LLANO 046,Reach-1,4
Up Type=0
Dn Type=3
Dn Slope=0.005
Boundary for River Rch & Prof#=LITTLE LLANO 046,Reach-1,5
Up Type=0
Dn Type=3
Dn Slope=0.005
Boundary for River Rch & Prof#=LITTLE LLANO 046,Reach-1,6
Up Type=0
Dn Type=3
Dn Slope=0.005
Boundary for River Rch & Prof#=LITTLE LLANO 046,Reach-1,7
Up Type=0
Dn Type=3
Dn Slope=0.005

--- LITTLE LLANO 046.g01 (geometry) ---

Geom Title=Existing Conditions

River Reach=LITTLE LLANO 046,Reach-1
Reach XY= 30
      2823039.75     10254003.00      2823119.00     10253993.00
      2823201.25     10253948.00      2823234.50     10253851.00
      2823294.00     10253839.00      2823350.00     10253787.00
      2823458.00     10253765.00      2823523.00     10253723.00
      2823646.00     10253683.00      2823735.50     10253621.00
      2823787.75     10253614.00      2823819.00     10253621.00
      2823831.50     10253675.00      2824108.50     10253837.00
      2824248.00     10253987.00      2824285.50     10254075.00
      2824431.50     10254083.00      2824467.50     10254110.00
      2824479.00     10254147.00      2824586.25     10254174.00
      2824686.50     10254258.00      2824861.25     10254290.00
      2824831.00     10254365.00      2824916.00     10254387.00
      2824949.50     10254466.00      2825194.50     10254415.00
      2825223.50     10254393.00      2825238.00     10254340.00
      2825398.75     10254292.00      2825511.25     10254387.00

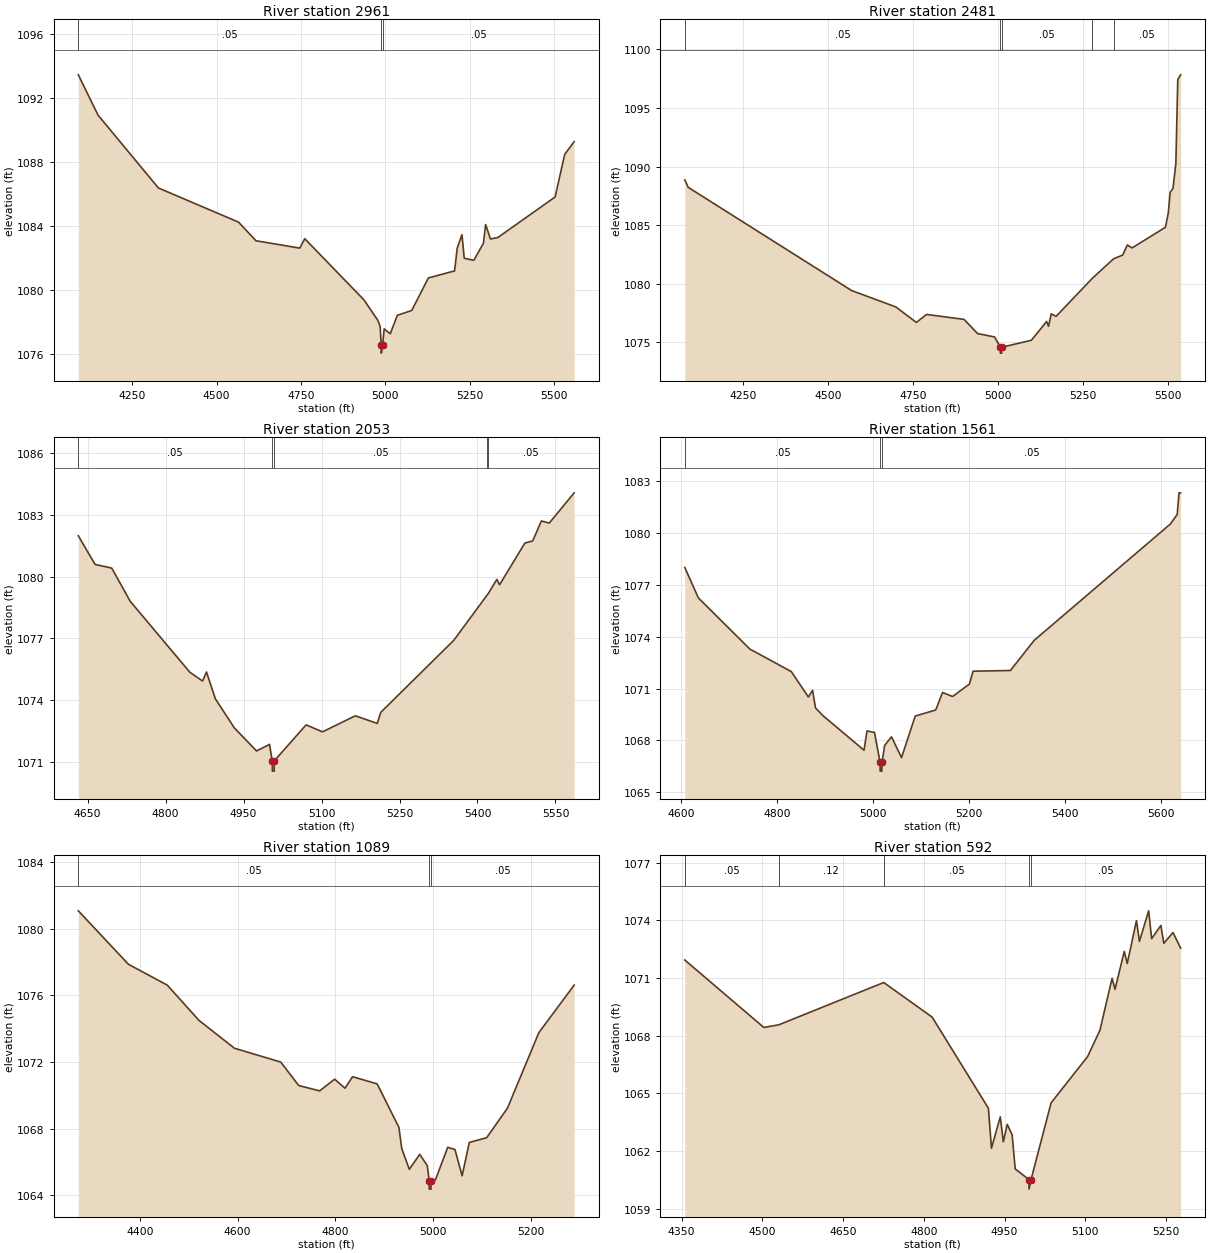
Type RM Length L Ch R = 1,2961,480,480,480
BEGIN DESCRIPTION:
LITTLE LLANO 046 6.0
END DESCRIPTION:
XS GIS Cut Line= 3
      2823455.67     10254753.07      2823227.25     10253872.00
      2822805.67     10253503.10
#Sta/Elev= 30
  4089.8 1093.44  4148.1 1090.93  4327.4 1086.38  4565.0 1084.25  4616.6 1083.09
  4746.5 1082.63  4761.2 1083.22  4936.9 1079.40  4978.2 1078.12  4984.8 1077.75
  4988.0 1076.58  4988.3 1076.08  4992.0 1076.58  4996.8 1077.59  5014.9 1077.29
  5035.8 1078.44  5078.5 1078.74  5127.9 1080.77  5205.7 1081.21  5213.3 1082.62
  5227.5 1083.47  5234.2 1082.00  5262.6 1081.87  5291.1 1082.93  5297.7 1084.10
  5312.0 1083.20  5333.8 1083.29  5503.7 1085.82  5532.2 1088.48  5560.2 1089.27
#Mann=3,-1,0
  4089.8    0.05       0  4988.0    0.03       0  4992.0    0.05       0
Bank Sta=4988,4992
Exp/Cntr=0.3,0.1

Type RM Length L Ch R = 1,2481,428,428,428
BEGIN DESCRIPTION:
LITTLE LLANO 046 5.0
END DESCRIPTION:
XS GIS Cut Line= 3
      2823605.68     10254603.12      2823646.00     10253683.00
      2823405.68     10253203.11
#Sta/Elev= 30
  4079.0 1088.86  4089.0 1088.23  4569.5 1079.42  4699.6 1078.02  4759.7 1076.70
  4789.7 1077.38  4899.8 1076.96  4939.8 1075.75  4989.9 1075.46  5006.7 1074.58
  5006.9 1074.08  5010.4 1074.08  5010.7 1074.58  5098.1 1075.18  5142.8 1076.78
  5148.4 1076.37  5156.4 1077.43  5170.7 1077.22  5276.9 1080.46  5339.7 1082.13
  5366.3 1082.45  5380.1 1083.31  5394.2 1083.06  5492.0 1084.82  5500.4 1086.03
  5506.0 1087.80  5514.3 1088.14  5522.7 1090.26  5528.3 1097.42  5536.7 1097.83
#Mann=5,-1,0
  4079.0    0.05       0  5006.7    0.03       0  5010.7    0.05       0
  5276.9    0.12       0  5339.7    0.05       0
Bank Sta=5006.7,5010.7
Exp/Cntr=0.3,0.1

Type RM Length L Ch R = 1,2053,492,492,492
BEGIN DESCRIPTION:
LITTLE LLANO 046 4.0
END DESCRIPTION:
XS GIS Cut Line= 3
      2823855.67     10254103.16      2823987.75     10253760.00
      2823805.68     10253203.11
#Sta/Elev= 30
  4632.3 1081.99  4664.5 1080.60  4696.6 1080.42  4732.0 1078.81  4846.7 1075.36
  4871.2 1074.93  4878.8 1075.37  4895.8 1074.07  4932.4 1072.65  4975.1 1071.53
  5000.0 1071.85  5005.2 1071.05  5005.5 1070.55  5009.0 1070.55  5009.2 1071.05
  5070.4 1072.80  5101.9 1072.46  5165.1 1073.24  5207.1 1072.87  5214.1 1073.41
  5354.4 1076.91  5418.5 1079.11  5420.9 1079.19  5437.2 1079.87  5442.5 1079.61
  5491.2 1081.64  5506.2 1081.74  5522.8 1082.71  5538.1 1082.61  5585.9 1084.08
#Mann=5,-1,0
  4632.3    0.05       0  5005.2    0.03       0  5009.2    0.05       0
  5418.5    0.12       0  5420.9    0.05       0
Bank Sta=5005.2,5009.2
Exp/Cntr=0.3,0.1

Type RM Length L Ch R = 1,1561,472,472,472
BEGIN DESCRIPTION:
LITTLE LLANO 046 3.0
END DESCRIPTION:
XS GIS Cut Line= 3
      2824105.71     10254403.07      2824331.50     10254083.00
      2824755.69     10253603.10
#Sta/Elev= 30
  4608.3 1077.99  4636.6 1076.23  4743.7 1073.28  4829.9 1071.98  4865.6 1070.51
  4874.3 1070.90  4880.4 1069.88  4895.2 1069.45  4981.4 1067.44  4987.6 1068.55
  5003.3 1068.46  5014.9 1066.73  5015.1 1066.23  5018.6 1066.23  5018.9 1066.73
  5024.4 1067.72  5038.6 1068.21  5059.5 1067.01  5088.0 1069.41  5130.7 1069.76
  5144.9 1070.77  5165.8 1070.54  5200.9 1071.26  5208.4 1072.00  5286.2 1072.04
  5335.6 1073.78  5619.2 1080.50  5633.4 1081.05  5637.2 1082.30  5640.5 1082.30
#Mann=3,-1,0
  4608.3    0.05       0  5014.9    0.03       0  5018.9    0.05       0
Bank Sta=5014.9,5018.9
Exp/Cntr=0.3,0.1

Type RM Length L Ch R = 1,1089,497,497,497
BEGIN DESCRIPTION:
LITTLE LLANO 046 2.0
END DESCRIPTION:
XS GIS Cut Line= 3
      2824105.67     10254653.12      2824723.50     10254273.00
      2824955.68     10254103.11
#Sta/Elev= 30
  4274.6 1081.08  4377.0 1077.87  4456.3 1076.62  4521.2 1074.50  4593.5 1072.83
  4688.2 1072.00  4724.9 1070.59  4767.7 1070.27  4798.3 1070.97  4819.5 1070.43
  4834.9 1071.12  4885.2 1070.69  4929.6 1068.08  4935.5 1066.80  4950.9 1065.56
  4972.2 1066.46  4987.6 1065.78  4991.5 1064.87  4991.7 1064.37  4995.2 1064.37
  4995.5 1064.87  5004.1 1064.92  5029.4 1066.88  5044.1 1066.75  5058.8 1065.17
  5073.4 1067.17  5109.0 1067.46  5151.4 1069.23  5215.5 1073.76  5287.7 1076.62
#Mann=3,-1,0
  4274.6    0.05       0  4991.5    0.03       0  4995.5    0.05       0
Bank Sta=4991.5,4995.5
Exp/Cntr=0.3,0.1

Type RM Length L Ch R = 1,592,0,0,0
BEGIN DESCRIPTION:
LITTLE LLANO 046 1.0
END DESCRIPTION:
XS GIS Cut Line= 3
      2824455.70     10254753.10      2825025.50     10254453.00
      2824905.70     10254203.14
#Sta/Elev= 30
  4356.0 1071.94  4502.9 1068.43  4530.7 1068.57  4725.6 1070.77  4815.5 1068.97
  4920.0 1064.23  4925.7 1062.15  4942.1 1063.78  4947.7 1062.48  4955.0 1063.39
  4964.1 1062.85  4969.8 1061.07  4995.3 1060.52  4995.5 1060.02  4999.3 1060.52
  5036.5 1064.51  5104.4 1066.92  5127.1 1068.28  5149.8 1070.99  5155.3 1070.42
  5172.4 1072.39  5178.0 1071.76  5195.1 1073.99  5200.6 1072.91  5217.7 1074.50
  5223.3 1073.05  5240.4 1073.74  5245.9 1072.81  5263.0 1073.37  5277.1 1072.56
#Mann=5,-1,0
  4356.0    0.05       0  4530.7    0.12       0  4725.6    0.05       0
  4995.3    0.05       0  4999.3    0.05       0
Bank Sta=4995.3,4999.3
Exp/Cntr=0.3,0.1

Chan Stop Cuts=-1