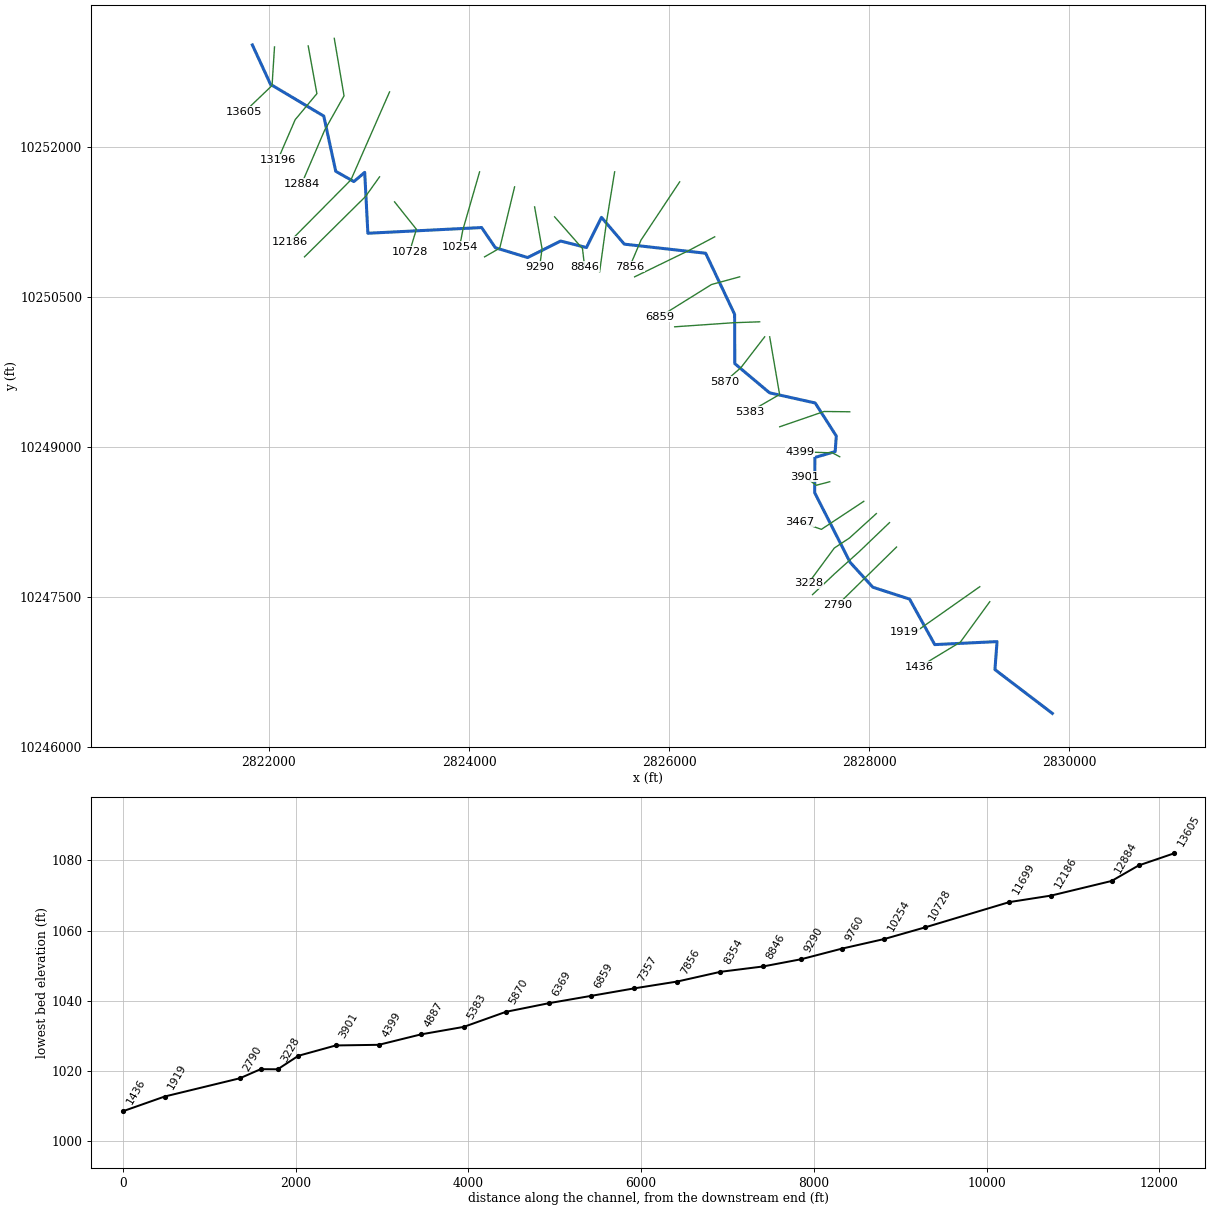
--- LITTLE LLANO 047.prj (project) ---

Proj Title=LITTLE LLANO 047 Base Level Engineering
Current Plan=p01
Default Exp/Contr=0.3,0.1
English Units
Geom File=g01
Flow File=f01
Plan File=p01
BEGIN DESCRIPTION:
LITTLE LLANO 047
END DESCRIPTION:

--- LITTLE LLANO 047.p01 (plan) ---

Plan Title=Multiple Run
Short Identifier=Multiple
Geom File=g01
Flow File=f01
Subcritical Flow
K Sum by GR= 0
Std Step Tol= 0.01
Critical Tol= 0.01
Num of Std Step Trials= 20
Max Error Tol= 0.3
Flow Tol Ratio= 0.001
Split Flow NTrial= 30
Split Flow Tol= 0.02
Split Flow Ratio= 0.02
Log Output Level= 0
Friction Slope Method= 1
Unsteady Friction Slope Method= 2
Unsteady Bridges Friction Slope Method= 1
Parabolic Critical Depth
Global Vel Dist=  1 , 1 , 1
Global Log Level= 0
CheckData=True
Encroach Param= -1, 0, 0, 0
BEGIN DESCRIPTION:
Multiple Run
END DESCRIPTION:

--- LITTLE LLANO 047.f01 (steady flow) ---

Flow Title=Multiple
Number of Profiles=7
Profile Names=10-year,25-year,50-year,1pct_min,100-year,1pct_plu,500-year
River Rch & RM= LITTLE LLANO 047,Reach-1,13605
     509     840     856     575    1115    2164    1496
River Rch & RM= LITTLE LLANO 047,Reach-1,3030
     783    1320    1502    1027    1997    3883    2675
Boundary for River Rch & Prof#=LITTLE LLANO 047,Reach-1,1
Up Type=0
Dn Type=3
Dn Slope=0.005
Boundary for River Rch & Prof#=LITTLE LLANO 047,Reach-1,2
Up Type=0
Dn Type=3
Dn Slope=0.005
Boundary for River Rch & Prof#=LITTLE LLANO 047,Reach-1,3
Up Type=0
Dn Type=3
Dn Slope=0.005
Boundary for River Rch & Prof#=LITTLE LLANO 047,Reach-1,4
Up Type=0
Dn Type=3
Dn Slope=0.005
Boundary for River Rch & Prof#=LITTLE LLANO 047,Reach-1,5
Up Type=0
Dn Type=3
Dn Slope=0.005
Boundary for River Rch & Prof#=LITTLE LLANO 047,Reach-1,6
Up Type=0
Dn Type=3
Dn Slope=0.005
Boundary for River Rch & Prof#=LITTLE LLANO 047,Reach-1,7
Up Type=0
Dn Type=3
Dn Slope=0.005

--- LITTLE LLANO 047.g01 (geometry) ---

Geom Title=Existing Conditions

River Reach=LITTLE LLANO 047,Reach-1
Reach XY= 30
      2821834.25     10253023.00      2822015.75     10252629.00
      2822548.25     10252311.00      2822667.75     10251759.00
      2822849.00     10251656.00      2822957.25     10251748.00
      2822989.00     10251139.00      2824126.00     10251196.00
      2824263.50     10250994.00      2824586.50     10250896.00
      2824915.50     10251061.00      2825174.00     10250996.00
      2825324.00     10251298.00      2825552.50     10251030.00
      2826365.75     10250939.00      2826655.00     10250328.00
      2826656.75     10249835.00      2827004.00     10249543.00
      2827460.50     10249441.00      2827671.25     10249111.00
      2827660.25     10248955.00      2827457.50     10248896.00
      2827455.25     10248544.00      2827809.50     10247847.00
      2828036.75     10247598.00      2828404.25     10247479.00
      2828655.50     10247024.00      2829278.25     10247054.00
      2829257.25     10246774.00      2829831.00     10246336.00

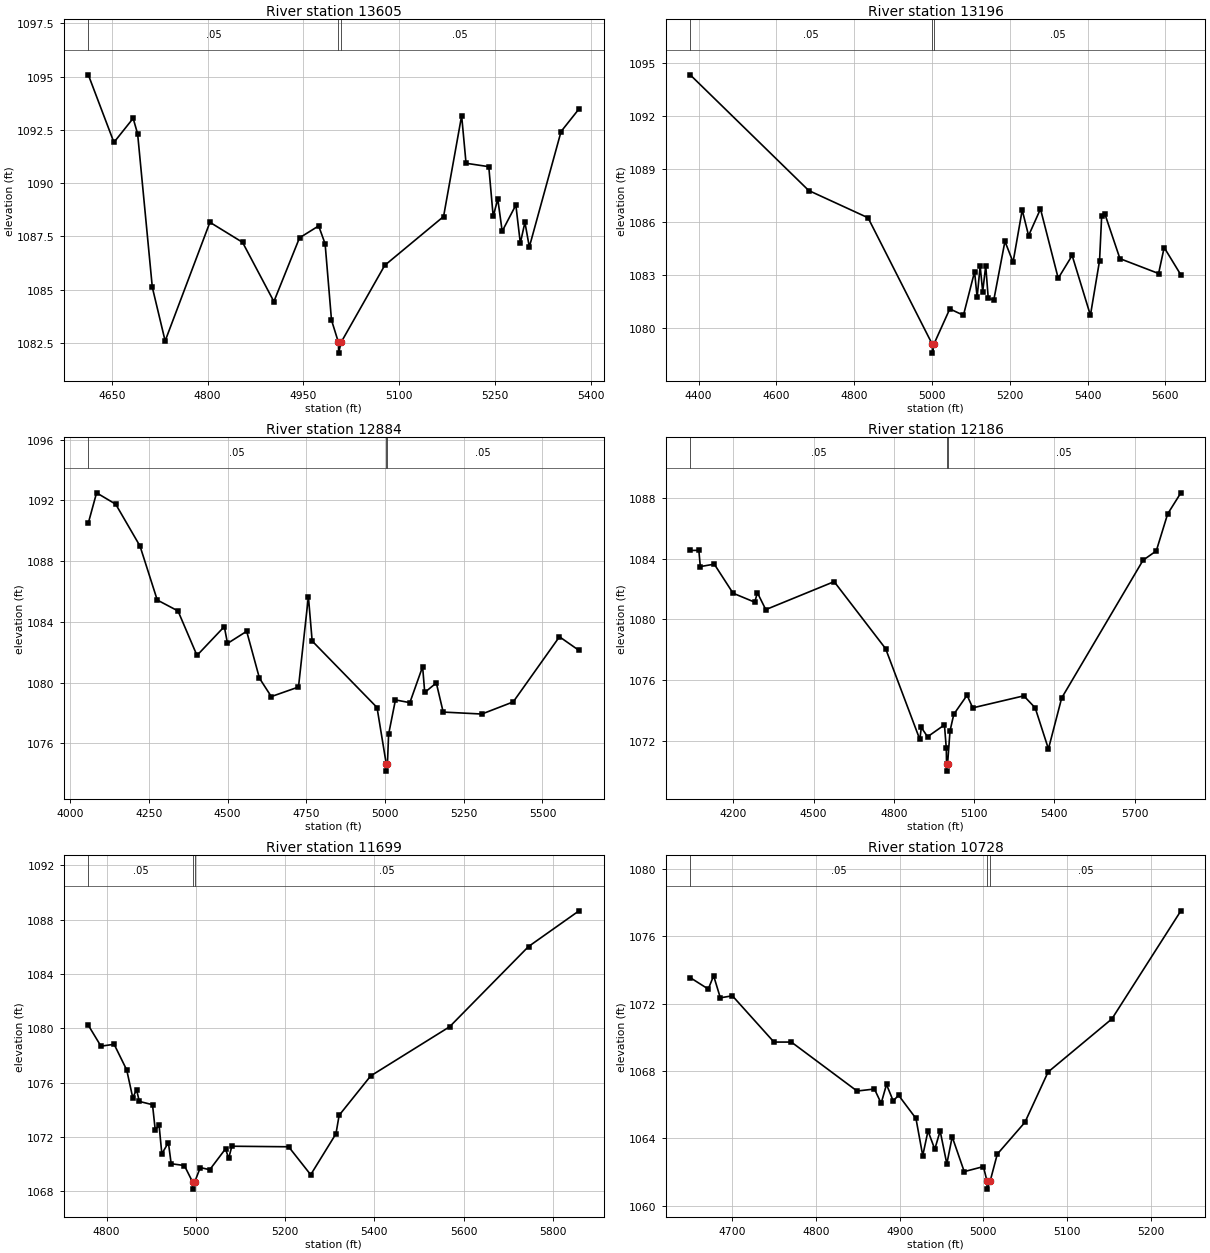
Type RM Length L Ch R = 1,13605,409,409,409
BEGIN DESCRIPTION:
LITTLE LLANO 047 26.0
END DESCRIPTION:
XS GIS Cut Line= 3
      2822055.69     10253003.13      2822031.25     10252617.00
      2821755.71     10252353.14
#Sta/Elev= 30
  4613.1 1095.08  4653.2 1091.91  4683.3 1093.04  4690.3 1092.31  4713.3 1085.11
  4733.4 1082.59  4803.5 1088.16  4854.6 1087.22  4903.7 1084.44  4943.8 1087.43
  4973.8 1087.99  4983.9 1087.15  4993.9 1083.57  5004.8 1082.52  5005.1 1082.02
  5008.8 1082.52  5077.3 1086.14  5169.4 1088.43  5197.7 1093.16  5204.6 1090.93
  5240.2 1090.77  5247.1 1088.44  5254.3 1089.25  5261.2 1087.74  5282.6 1088.97
  5289.6 1087.18  5296.8 1088.16  5303.7 1087.00  5353.4 1092.42  5381.5 1093.48
#Mann=3,-1,0
  4613.1    0.05       0  5004.8    0.03       0  5008.8    0.05       0
Bank Sta=5004.8,5008.8
Exp/Cntr=0.3,0.1

Type RM Length L Ch R = 1,13196,312,312,312
BEGIN DESCRIPTION:
Mapping XS 1bb313a2
END DESCRIPTION:
XS GIS Cut Line= 4
      2822392.59     10253013.02      2822479.40     10252535.57
      2822262.38     10252275.15      2822088.76     10251873.65
#Sta/Elev= 30
  4378.3 1094.31  4683.1 1087.77  4835.6 1086.23  5000.8 1079.08  5001.1 1078.58
  5004.8 1079.08  5045.8 1081.08  5080.9 1080.72  5109.5 1083.18  5116.1 1081.74
  5123.9 1083.50  5130.4 1082.05  5138.2 1083.52  5144.7 1081.67  5159.0 1081.59
  5187.6 1084.90  5208.5 1083.72  5232.0 1086.67  5248.4 1085.22  5279.0 1086.73
  5324.6 1082.81  5360.4 1084.10  5407.4 1080.72  5430.9 1083.81  5436.3 1086.33
  5444.5 1086.45  5483.3 1083.92  5582.7 1083.08  5597.0 1084.55  5640.0 1083.00
#Mann=3,-1,0
  4378.3    0.05       0  5000.8    0.05       0  5004.8    0.05       0
Bank Sta=5000.8,5004.8
Exp/Cntr=0.3,0.1

Type RM Length L Ch R = 1,12884,698,698,698
BEGIN DESCRIPTION:
Mapping XS 95133f5a
END DESCRIPTION:
XS GIS Cut Line= 4
      2822653.01     10253088.92      2822750.66     10252513.87
      2822555.35     10252166.65      2822328.17     10251636.55
#Sta/Elev= 30
  4057.7 1090.51  4083.9 1092.50  4144.7 1091.75  4221.9 1088.99  4276.6 1085.44
  4342.5 1084.72  4402.8 1081.79  4489.6 1083.69  4499.7 1082.58  4560.6 1083.38
  4601.2 1080.29  4638.8 1079.08  4725.2 1079.71  4756.6 1085.67  4768.6 1082.74
  4974.6 1078.36  5003.7 1074.67  5003.9 1074.17  5007.7 1074.67  5011.4 1076.60
  5033.1 1078.86  5078.9 1078.68  5119.4 1081.05  5126.1 1079.35  5162.9 1079.98
  5184.7 1078.06  5307.4 1077.93  5407.2 1078.73  5554.0 1083.02  5616.1 1082.12
#Mann=3,-1,0
  4057.7    0.05       0  5003.7    0.05       0  5007.7    0.05       0
Bank Sta=5003.7,5007.7
Exp/Cntr=0.3,0.1

Type RM Length L Ch R = 1,12186,487,487,487
BEGIN DESCRIPTION:
LITTLE LLANO 047 23.0
END DESCRIPTION:
XS GIS Cut Line= 3
      2823205.68     10252553.10      2822819.75     10251673.00
      2822205.72     10251053.15
#Sta/Elev= 30
  4039.0 1084.53  4071.3 1084.54  4076.8 1083.47  4129.0 1083.63  4199.1 1081.72
  4280.1 1081.13  4290.1 1081.75  4321.4 1080.64  4576.9 1082.48  4769.3 1078.07
  4897.1 1072.10  4902.6 1072.89  4925.9 1072.28  4989.0 1073.06  4996.0 1071.51
  4996.8 1070.52  4997.1 1070.02  5000.8 1070.52  5009.9 1072.67  5024.0 1073.76
  5073.5 1075.01  5094.7 1074.18  5285.6 1074.97  5328.1 1074.18  5377.6 1071.48
  5427.1 1074.83  5731.2 1083.89  5780.6 1084.50  5823.0 1086.93  5872.5 1088.32
#Mann=3,-1,0
  4039.0    0.05       0  4996.8    0.03       0  5000.8    0.05       0
Bank Sta=4996.8,5000.8
Exp/Cntr=0.3,0.1

Type RM Length L Ch R = 1,11699,971,971,971
BEGIN DESCRIPTION:
LITTLE LLANO 047 22.0
END DESCRIPTION:
XS GIS Cut Line= 3
      2823105.67     10251703.10      2822965.75     10251507.00
      2822355.69     10250903.12
#Sta/Elev= 30
  4759.1 1080.22  4787.4 1078.68  4816.9 1078.82  4845.1 1076.93  4858.6 1074.89
  4867.2 1075.46  4873.4 1074.61  4902.9 1074.37  4909.0 1072.51  4917.6 1072.86
  4923.8 1070.75  4938.5 1071.58  4944.7 1070.02  4974.2 1069.89  4993.1 1068.65
  4993.3 1068.15  4997.1 1068.65  5009.9 1069.74  5031.1 1069.58  5066.5 1071.12
  5073.5 1070.41  5080.6 1071.31  5207.9 1071.27  5257.3 1069.21  5313.9 1072.23
  5321.0 1073.59  5391.7 1076.49  5568.5 1080.11  5745.3 1086.02  5858.4 1088.65
#Mann=3,-1,0
  4759.1    0.05       0  4993.1    0.03       0  4997.1    0.05       0
Bank Sta=4993.1,4997.1
Exp/Cntr=0.3,0.1

Type RM Length L Ch R = 1,10728,474,474,474
BEGIN DESCRIPTION:
LITTLE LLANO 047 20.0
END DESCRIPTION:
XS GIS Cut Line= 3
      2823255.70     10251453.09      2823474.00     10251179.00
      2823405.68     10250953.10
#Sta/Elev= 30
  4649.6 1073.55  4671.2 1072.87  4677.6 1073.66  4685.6 1072.35  4700.0 1072.47
  4749.7 1069.72  4770.5 1069.72  4849.0 1066.81  4869.8 1066.93  4877.8 1066.08
  4884.2 1067.20  4892.2 1066.22  4898.6 1066.56  4919.4 1065.18  4927.5 1062.97
  4933.8 1064.44  4941.9 1063.35  4948.3 1064.44  4956.3 1062.48  4962.7 1064.09
  4977.1 1062.02  5000.0 1062.32  5004.2 1061.48  5004.4 1060.98  5008.2 1061.48
  5016.6 1063.06  5049.6 1064.95  5077.3 1067.94  5153.6 1071.10  5236.0 1077.52
#Mann=3,-1,0
  4649.6    0.05       0  5004.2    0.03       0  5008.2    0.05       0
Bank Sta=5004.2,5008.2
Exp/Cntr=0.3,0.1

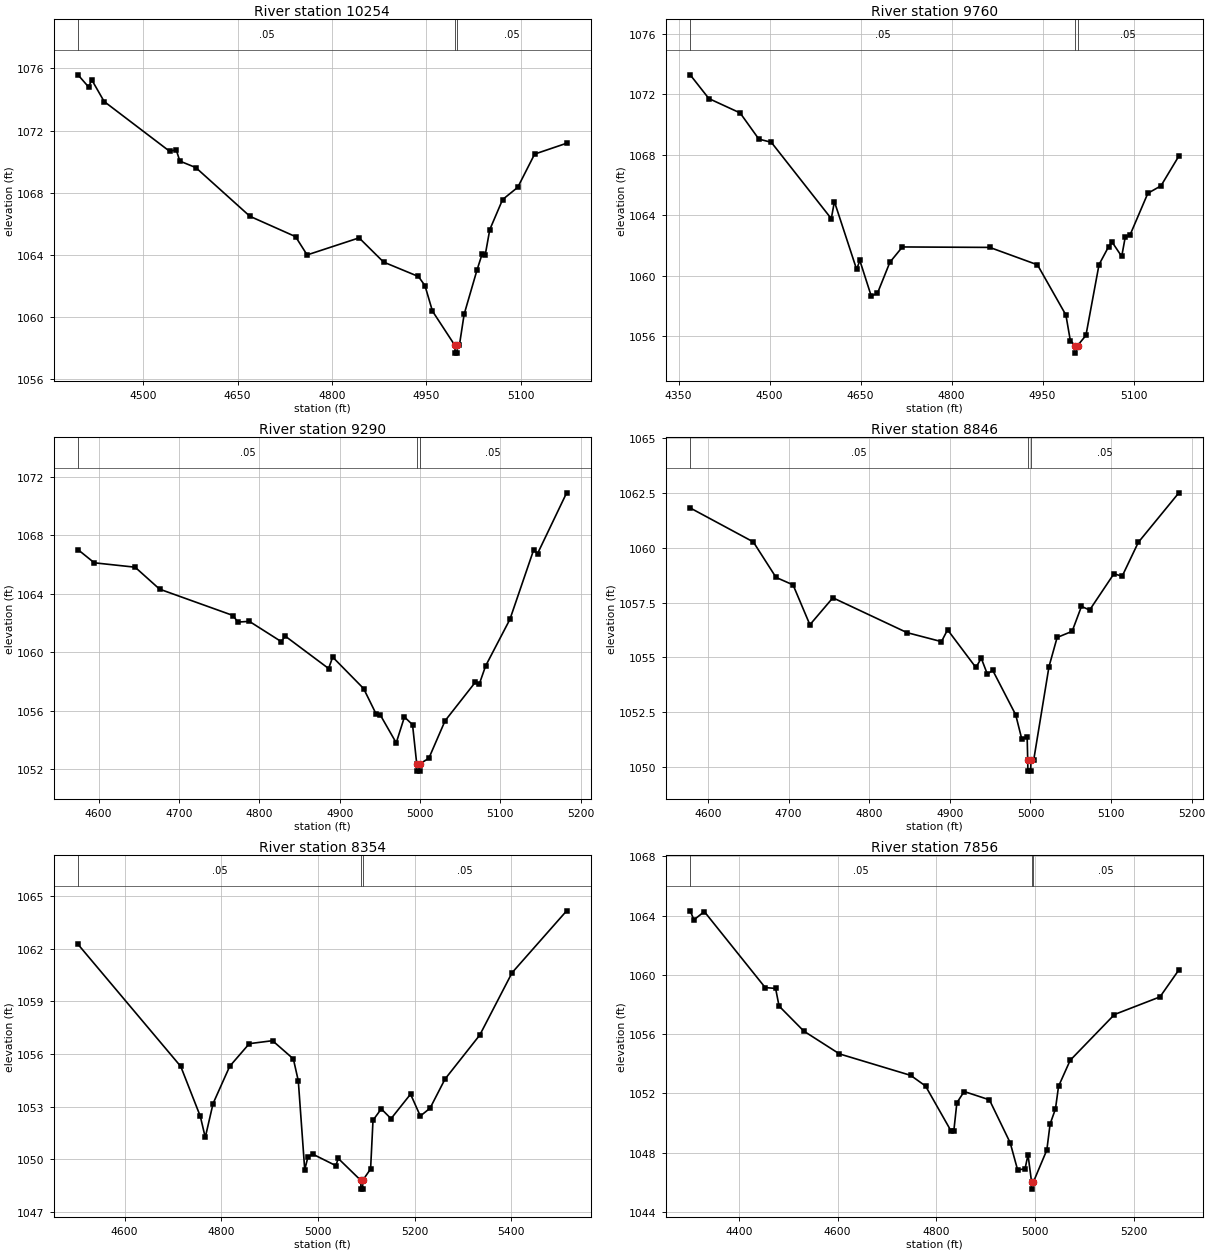
Type RM Length L Ch R = 1,10254,494,494,494
BEGIN DESCRIPTION:
LITTLE LLANO 047 19.0
END DESCRIPTION:
XS GIS Cut Line= 3
      2824105.68     10251753.09      2823938.50     10251173.00
      2823905.69     10251003.14
#Sta/Elev= 30
  4396.3 1075.59  4413.1 1074.81  4418.3 1075.26  4437.9 1073.87  4542.0 1070.66
  4552.4 1070.76  4558.2 1070.03  4583.6 1069.61  4669.6 1066.47  4742.1 1065.16
  4760.5 1063.98  4843.1 1065.08  4882.0 1063.52  4937.4 1062.59  4947.8 1062.00
  4959.7 1060.36  4995.3 1058.15  4995.6 1057.65  4999.1 1057.65  4999.3 1058.15
  5002.5 1058.15  5010.1 1060.16  5030.4 1062.99  5038.4 1064.01  5043.5 1063.96
  5050.8 1065.61  5071.2 1067.55  5095.3 1068.34  5122.1 1070.48  5173.0 1071.18
#Mann=3,-1,0
  4396.3    0.05       0  4995.3    0.03       0  4999.3    0.05       0
Bank Sta=4995.3,4999.3
Exp/Cntr=0.3,0.1

Type RM Length L Ch R = 1,9760,470,470,470
BEGIN DESCRIPTION:
LITTLE LLANO 047 18.0
END DESCRIPTION:
XS GIS Cut Line= 3
      2824455.68     10251603.09      2824307.25     10250990.00
      2824155.69     10250903.11
#Sta/Elev= 30
  4369.2 1073.29  4400.0 1071.72  4451.5 1070.77  4482.4 1069.04  4502.9 1068.83
  4601.8 1063.78  4606.9 1064.91  4643.6 1060.42  4648.8 1061.02  4667.6 1058.67
  4677.8 1058.84  4698.4 1060.90  4719.0 1061.91  4863.0 1061.88  4941.6 1060.73
  4988.5 1057.41  4995.8 1055.72  5003.7 1055.39  5003.9 1054.89  5007.7 1055.39
  5021.5 1056.06  5043.1 1060.74  5058.9 1061.93  5064.7 1062.23  5080.5 1061.28
  5086.2 1062.54  5094.0 1062.68  5123.6 1065.46  5145.2 1065.95  5174.7 1067.92
#Mann=3,-1,0
  4369.2    0.05       0  5003.7    0.03       0  5007.7    0.05       0
Bank Sta=5003.7,5007.7
Exp/Cntr=0.3,0.1

Type RM Length L Ch R = 1,9290,444,444,444
BEGIN DESCRIPTION:
LITTLE LLANO 047 17.0
END DESCRIPTION:
XS GIS Cut Line= 3
      2824655.68     10251403.12      2824730.25     10250984.00
      2824705.69     10250803.16
#Sta/Elev= 30
  4574.3 1067.01  4594.6 1066.11  4645.4 1065.81  4675.9 1064.31  4767.3 1062.51
  4773.2 1062.06  4787.6 1062.11  4827.2 1060.73  4832.3 1061.10  4886.2 1058.89
  4891.3 1059.67  4929.8 1057.52  4945.2 1055.80  4950.3 1055.74  4970.4 1053.81
  4980.6 1055.58  4990.7 1055.05  4995.9 1052.38  4996.2 1051.88  4999.7 1051.88
  4999.9 1052.38  5011.0 1052.76  5031.2 1055.32  5068.8 1057.95  5073.8 1057.83
  5081.6 1059.06  5111.9 1062.25  5141.3 1066.97  5146.3 1066.74  5182.5 1070.89
#Mann=3,-1,0
  4574.3    0.05       0  4995.9    0.03       0  4999.9    0.05       0
Bank Sta=4995.9,4999.9
Exp/Cntr=0.3,0.1

Type RM Length L Ch R = 1,8846,492,492,492
BEGIN DESCRIPTION:
LITTLE LLANO 047 16.0
END DESCRIPTION:
XS GIS Cut Line= 3
      2824855.68     10251303.12      2825134.25     10250986.00
      2825155.68     10250803.15
#Sta/Elev= 30
  4577.9 1061.82  4656.2 1060.27  4684.4 1058.65  4705.5 1058.31  4726.4 1056.49
  4754.9 1057.72  4846.9 1056.13  4889.6 1055.72  4897.2 1056.26  4932.3 1054.54
  4939.0 1054.96  4946.5 1054.24  4953.2 1054.41  4981.7 1052.38  4989.2 1051.28
  4995.9 1051.38  4996.6 1050.31  4996.8 1049.81  5000.3 1049.81  5000.6 1050.31
  5004.0 1050.31  5023.0 1054.58  5033.1 1055.91  5051.7 1056.19  5063.3 1057.33
  5073.4 1057.16  5103.6 1058.82  5113.7 1058.70  5133.8 1060.25  5184.1 1062.51
#Mann=3,-1,0
  4577.9    0.05       0  4996.6    0.03       0  5000.6    0.05       0
Bank Sta=4996.6,5000.6
Exp/Cntr=0.3,0.1

Type RM Length L Ch R = 1,8354,498,498,498
BEGIN DESCRIPTION:
LITTLE LLANO 047 15.0
END DESCRIPTION:
XS GIS Cut Line= 3
      2825455.68     10251753.07      2825376.00     10251263.00
      2825305.69     10250753.13
#Sta/Elev= 30
  4503.5 1062.26  4716.2 1055.29  4756.7 1052.44  4766.9 1051.24  4783.0 1053.17
  4817.5 1055.30  4858.0 1056.59  4906.1 1056.76  4949.2 1055.72  4959.4 1054.47
  4972.7 1049.40  4979.6 1050.15  4989.8 1050.28  5037.1 1049.63  5042.1 1050.04
  5088.7 1048.79  5089.0 1048.29  5092.5 1048.29  5092.7 1048.79  5109.0 1049.44
  5114.0 1052.22  5131.1 1052.87  5151.3 1052.31  5191.7 1053.71  5211.9 1052.46
  5232.1 1052.91  5263.0 1054.57  5334.9 1057.08  5401.8 1060.64  5514.7 1064.17
#Mann=3,-1,0
  4503.5    0.05       0  5088.7    0.03       0  5092.7    0.05       0
Bank Sta=5088.7,5092.7
Exp/Cntr=0.3,0.1

Type RM Length L Ch R = 1,7856,499,499,499
BEGIN DESCRIPTION:
LITTLE LLANO 047 14.0
END DESCRIPTION:
XS GIS Cut Line= 3
      2826105.70     10251653.14      2825719.50     10251071.00
      2825605.67     10250803.08
#Sta/Elev= 30
  4301.4 1064.32  4309.0 1063.71  4330.0 1064.27  4453.3 1059.14  4474.4 1059.08
  4481.4 1057.89  4531.5 1056.20  4603.7 1054.66  4748.0 1053.21  4778.1 1052.49
  4829.3 1049.48  4835.3 1049.45  4841.5 1051.36  4856.3 1052.12  4907.4 1051.56
  4949.5 1048.66  4964.6 1046.82  4979.6 1046.91  4985.6 1047.85  4992.7 1046.03
  4992.9 1045.53  4996.7 1046.03  5023.7 1048.17  5030.3 1049.92  5041.2 1050.95
  5047.4 1052.47  5071.0 1054.23  5160.7 1057.32  5252.9 1058.51  5291.1 1060.33
#Mann=3,-1,0
  4301.4    0.05       0  4992.7    0.03       0  4996.7    0.05       0
Bank Sta=4992.7,4996.7
Exp/Cntr=0.3,0.1

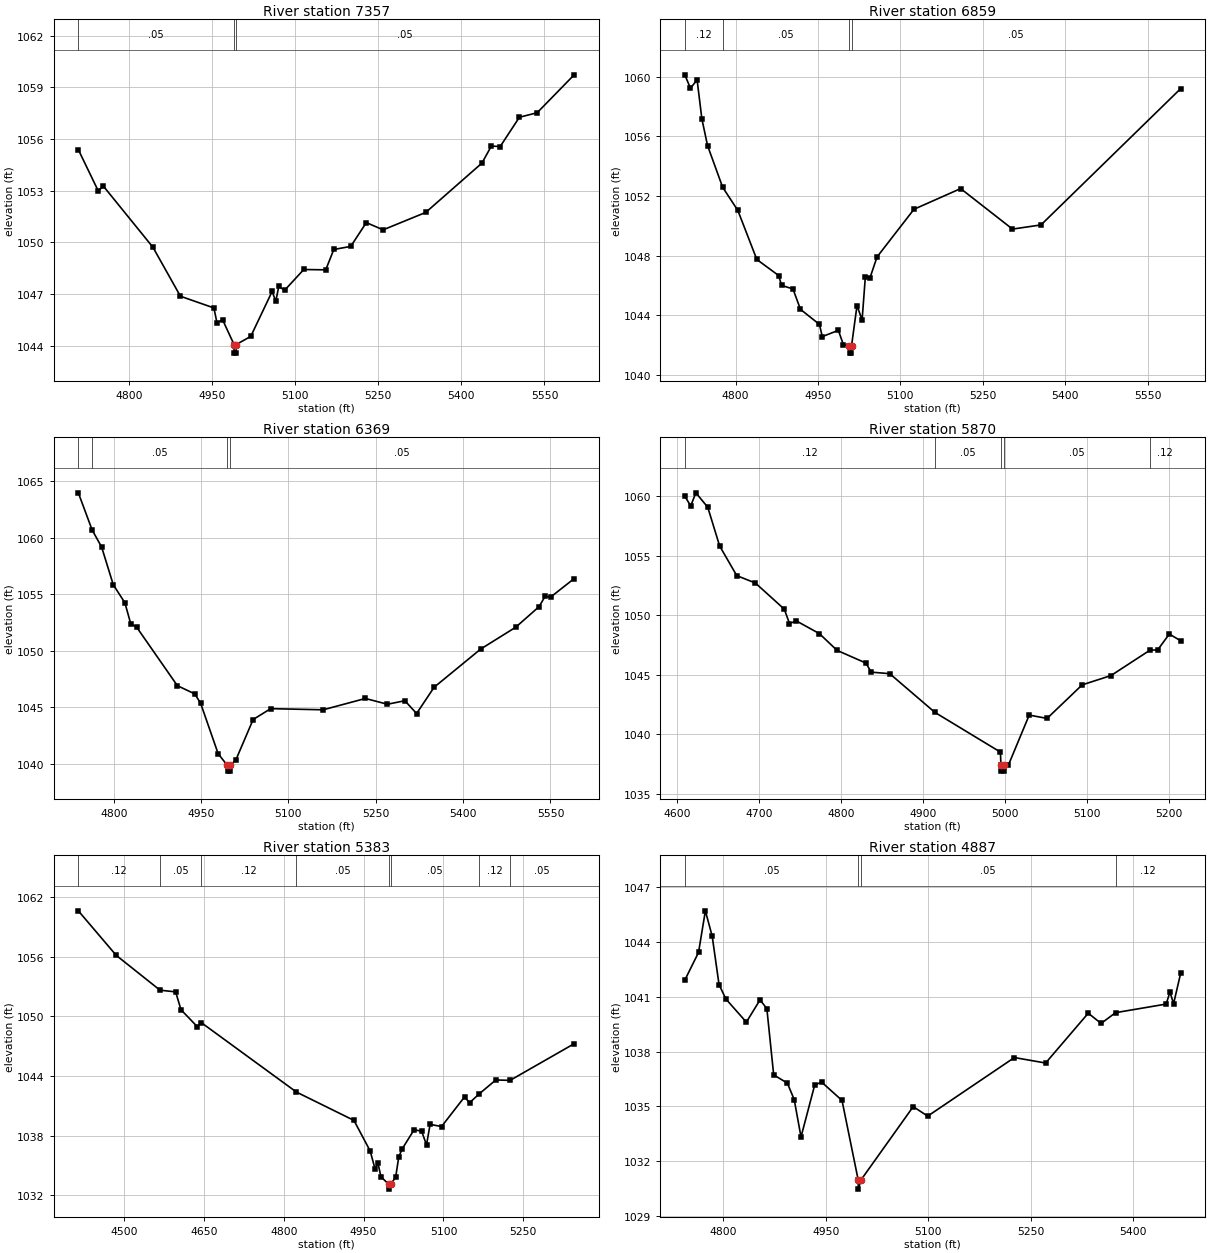
Type RM Length L Ch R = 1,7357,498,498,498
BEGIN DESCRIPTION:
LITTLE LLANO 047 13.0
END DESCRIPTION:
XS GIS Cut Line= 3
      2826455.70     10251103.12      2826198.50     10250967.00
      2825655.65     10250703.09
#Sta/Elev= 30
  4709.0 1055.38  4744.9 1052.99  4754.3 1053.26  4843.6 1049.72  4893.2 1046.88
  4953.6 1046.20  4959.2 1045.33  4969.2 1045.52  4989.9 1044.08  4990.1 1043.58
  4993.6 1043.58  4993.9 1044.08  5020.1 1044.55  5058.7 1047.16  5065.2 1046.58
  5070.7 1047.46  5081.0 1047.22  5115.8 1048.43  5155.4 1048.41  5169.9 1049.59
  5200.5 1049.77  5228.6 1051.15  5258.9 1050.73  5335.8 1051.74  5437.2 1054.60
  5454.2 1055.59  5470.1 1055.56  5504.8 1057.26  5536.8 1057.52  5603.6 1059.72
#Mann=3,-1,0
  4709.0    0.05       0  4989.9    0.05       0  4993.9    0.05       0
Bank Sta=4989.9,4993.9
Exp/Cntr=0.3,0.1

Type RM Length L Ch R = 1,6859,490,490,490
BEGIN DESCRIPTION:
LITTLE LLANO 047 12.0
END DESCRIPTION:
XS GIS Cut Line= 3
      2826705.65     10250703.10      2826423.50     10250626.00
      2825905.72     10250303.13
#Sta/Elev= 30
  4707.5 1060.14  4717.8 1059.24  4729.9 1059.80  4738.6 1057.18  4748.9 1055.39
  4776.4 1052.59  4804.1 1051.03  4838.6 1047.74  4878.4 1046.66  4883.7 1046.00
  4904.4 1045.76  4918.1 1044.39  4952.6 1043.38  4957.8 1042.56  4987.1 1042.98
  4996.3 1042.01  5007.1 1041.95  5007.4 1041.45  5010.9 1041.45  5011.1 1041.95
  5021.0 1044.64  5030.3 1043.68  5036.2 1046.57  5044.6 1046.50  5057.5 1047.91
  5124.7 1051.11  5209.7 1052.50  5304.1 1049.78  5356.0 1050.06  5610.2 1059.21
#Mann=4,-1,0
  4707.5    0.12       0  4776.4    0.05       0  5007.1    0.03       0
  5011.1    0.05       0
Bank Sta=5007.1,5011.1
Exp/Cntr=0.3,0.1

Type RM Length L Ch R = 1,6369,499,499,499
BEGIN DESCRIPTION:
LITTLE LLANO 047 11.0
END DESCRIPTION:
XS GIS Cut Line= 3
      2826905.64     10250253.11      2826645.00     10250244.00
      2826055.72     10250203.11
#Sta/Elev= 30
  4739.2 1063.95  4762.8 1060.68  4779.2 1059.16  4799.2 1055.83  4819.2 1054.23
  4829.2 1052.38  4839.2 1052.09  4909.3 1046.91  4939.3 1046.18  4949.3 1045.34
  4979.3 1040.90  4995.2 1039.86  4995.4 1039.36  4998.9 1039.36  4999.2 1039.86
  5009.3 1040.30  5039.4 1043.92  5069.5 1044.88  5159.7 1044.78  5232.2 1045.78
  5270.0 1045.27  5300.0 1045.58  5320.1 1044.45  5350.2 1046.77  5430.3 1050.15
  5490.5 1052.08  5530.6 1053.90  5540.6 1054.79  5550.6 1054.75  5590.7 1056.37
#Mann=4,-1,0
  4739.2    0.12       0  4762.8    0.05       0  4995.2    0.03       0
  4999.2    0.05       0
Bank Sta=4995.2,4999.2
Exp/Cntr=0.3,0.1

Type RM Length L Ch R = 1,5870,487,487,487
BEGIN DESCRIPTION:
LITTLE LLANO 047 10.0
END DESCRIPTION:
XS GIS Cut Line= 3
      2826955.66     10250103.09      2826717.50     10249794.00
      2826555.65     10249653.08
#Sta/Elev= 30
  4609.8 1060.00  4617.0 1059.18  4623.3 1060.28  4637.8 1059.07  4652.3 1055.81
  4673.2 1053.32  4695.9 1052.70  4731.2 1050.50  4737.5 1049.29  4745.7 1049.52
  4773.9 1048.45  4795.5 1047.04  4830.8 1045.97  4837.1 1045.21  4859.8 1045.08
  4914.8 1041.83  4994.8 1038.49  4995.4 1037.39  4995.7 1036.89  4999.2 1036.89
  4999.4 1037.39  5004.5 1037.39  5029.9 1041.60  5051.7 1041.32  5094.5 1044.14
  5129.6 1044.92  5177.1 1047.05  5186.6 1047.08  5200.8 1048.41  5214.6 1047.85
#Mann=5,-1,0
  4609.8    0.12       0  4914.8    0.05       0  4995.4    0.05       0
  4999.4    0.05       0  5177.1    0.12       0
Bank Sta=4995.4,4999.4
Exp/Cntr=0.3,0.1

Type RM Length L Ch R = 1,5383,496,496,496
BEGIN DESCRIPTION:
LITTLE LLANO 047 9.0
END DESCRIPTION:
XS GIS Cut Line= 3
      2827005.68     10250103.16      2827104.75     10249526.00
      2826805.72     10249353.13
#Sta/Elev= 30
  4414.4 1060.63  4485.5 1056.15  4567.8 1052.64  4597.1 1052.47  4607.2 1050.67
  4637.7 1048.97  4645.4 1049.37  4824.0 1042.38  4931.9 1039.53  4962.3 1036.46
  4971.7 1034.62  4976.8 1035.27  4982.6 1033.86  4996.9 1033.11  4997.2 1032.61
  5000.9 1033.11  5010.2 1033.80  5016.0 1035.83  5022.0 1036.62  5045.1 1038.61
  5059.1 1038.42  5068.2 1037.07  5074.9 1039.13  5096.4 1038.91  5139.5 1041.89
  5149.1 1041.31  5166.9 1042.19  5198.3 1043.60  5225.1 1043.56  5345.4 1047.25
#Mann=8,-1,0
  4414.4    0.12       0  4567.8    0.05       0  4645.4    0.12       0
  4824.0    0.05       0  4996.9    0.05       0  5000.9    0.05       0
  5166.9    0.12       0  5225.1    0.05       0
Bank Sta=4996.9,5000.9
Exp/Cntr=0.3,0.1

Type RM Length L Ch R = 1,4887,488,488,488
BEGIN DESCRIPTION:
LITTLE LLANO 047 8.0
END DESCRIPTION:
XS GIS Cut Line= 3
      2827805.73     10249353.11      2827549.25     10249356.00
      2827105.66     10249203.10
#Sta/Elev= 30
  4743.5 1041.92  4763.6 1043.44  4773.6 1045.72  4783.6 1044.33  4793.6 1041.68
  4803.6 1040.89  4833.6 1039.62  4853.6 1040.84  4863.6 1040.36  4873.6 1036.73
  4893.6 1036.28  4903.6 1035.38  4913.6 1033.33  4933.6 1036.17  4943.6 1036.34
  4973.6 1035.33  4997.3 1030.97  4997.5 1030.47  5001.3 1030.97  5077.8 1034.99
  5099.0 1034.47  5225.9 1037.68  5271.6 1037.38  5334.0 1040.11  5352.8 1039.55
  5374.0 1040.14  5448.0 1040.61  5453.6 1041.27  5458.9 1040.63  5469.2 1042.29
#Mann=4,-1,0
  4743.5    0.05       0  4997.3    0.05       0  5001.3    0.05       0
  5374.0    0.12       0
Bank Sta=4997.3,5001.3
Exp/Cntr=0.3,0.1

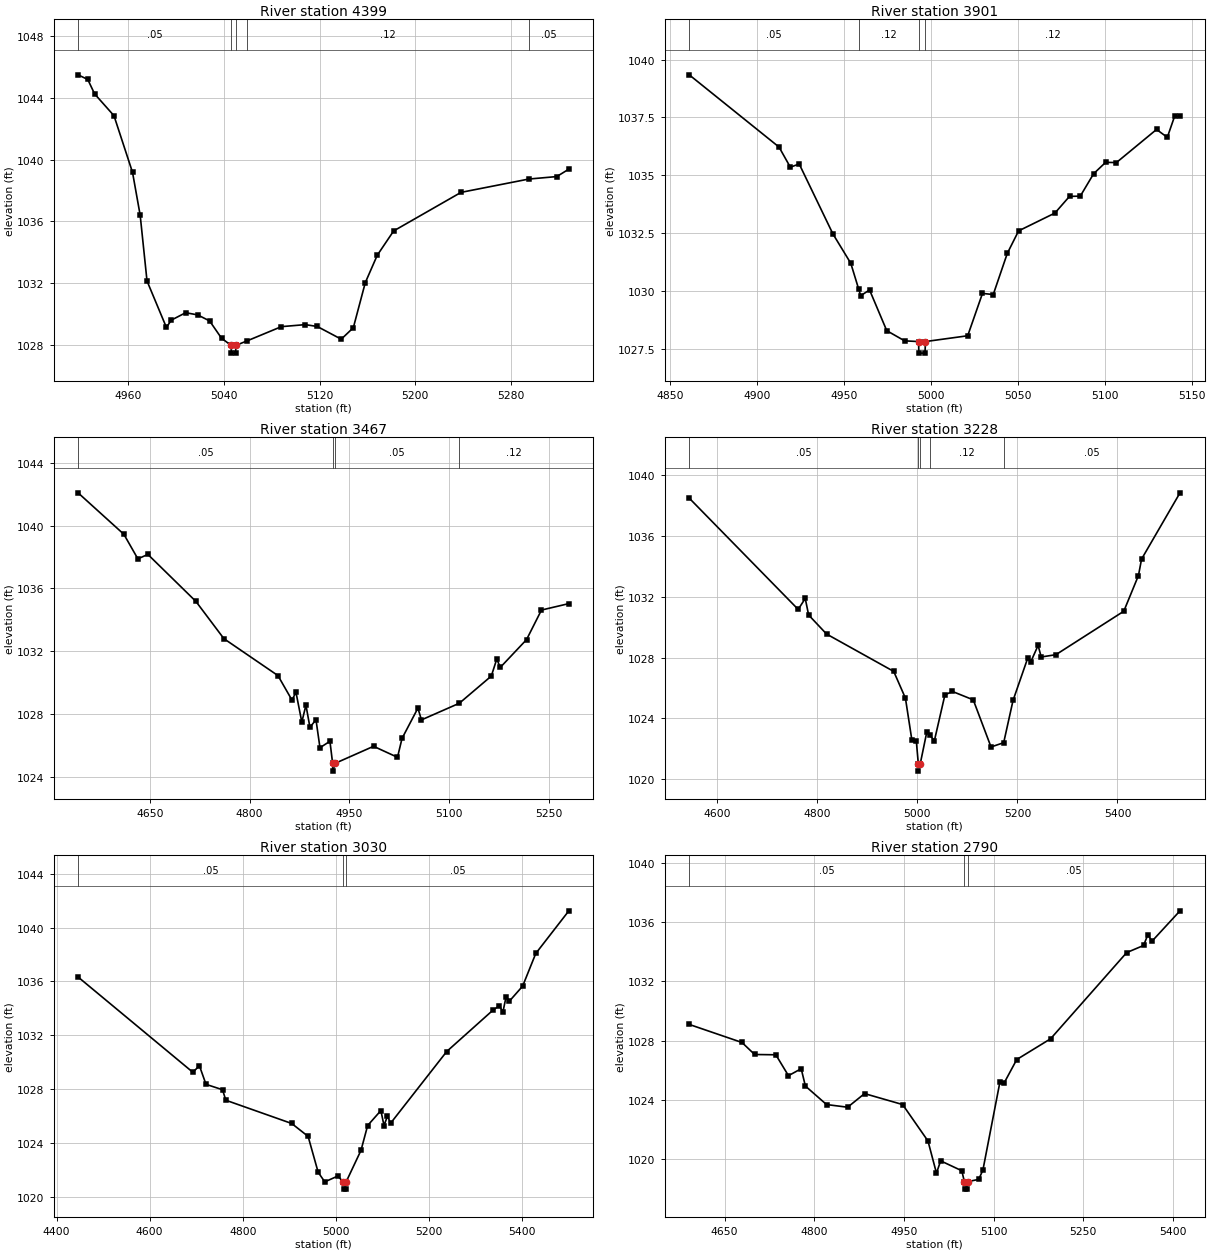
Type RM Length L Ch R = 1,4399,498,498,498
BEGIN DESCRIPTION:
LITTLE LLANO 047 7.0
END DESCRIPTION:
XS GIS Cut Line= 3
      2827705.71     10248903.10      2827633.75     10248942.00
      2827305.64     10248953.11
#Sta/Elev= 30
  4918.2 1045.47  4926.3 1045.17  4932.0 1044.24  4948.2 1042.83  4963.7 1039.17
  4970.1 1036.40  4975.8 1032.16  4992.0 1029.16  4996.1 1029.63  5008.1 1030.11
  5018.1 1029.97  5028.1 1029.58  5038.1 1028.46  5046.1 1028.00  5046.3 1027.50
  5049.8 1027.50  5050.1 1028.00  5059.7 1028.30  5088.1 1029.21  5108.1 1029.34
  5118.1 1029.22  5138.1 1028.40  5148.2 1029.14  5158.2 1032.05  5168.2 1033.82
  5181.9 1035.39  5238.2 1037.88  5294.8 1038.74  5318.2 1038.90  5328.3 1039.38
#Mann=5,-1,0
  4918.2    0.05       0  5046.1    0.05       0  5050.1    0.05       0
  5059.7    0.12       0  5294.8    0.05       0
Bank Sta=5046.1,5050.1
Exp/Cntr=0.3,0.1

Type RM Length L Ch R = 1,3901,434,434,434
BEGIN DESCRIPTION:
LITTLE LLANO 047 6.0
END DESCRIPTION:
XS GIS Cut Line= 3
      2827605.70     10248653.12      2827471.00     10248618.00
      2827355.70     10248703.10
#Sta/Elev= 30
  4860.8 1039.34  4912.5 1036.22  4919.0 1035.35  4924.1 1035.49  4943.5 1032.47
  4953.8 1031.20  4958.4 1030.07  4959.5 1029.80  4964.6 1030.05  4974.5 1028.29
  4984.8 1027.85  4992.8 1027.82  4993.0 1027.32  4996.5 1027.32  4996.8 1027.82
  5021.1 1028.07  5029.6 1029.90  5035.8 1029.85  5043.9 1031.63  5050.4 1032.60
  5071.3 1033.37  5079.7 1034.09  5085.9 1034.10  5093.6 1035.07  5100.5 1035.56
  5106.7 1035.55  5129.8 1036.98  5136.0 1036.64  5140.2 1037.55  5143.3 1037.55
#Mann=4,-1,0
  4860.8    0.05       0  4958.4    0.12       0  4992.8    0.07       0
  4996.8    0.12       0
Bank Sta=4992.8,4996.8
Exp/Cntr=0.3,0.1

Type RM Length L Ch R = 1,3467,239,239,239
BEGIN DESCRIPTION:
LITTLE LLANO 047 5.0
END DESCRIPTION:
XS GIS Cut Line= 3
      2827946.40     10248457.27      2827522.42     10248176.88
      2827305.65     10248253.13
#Sta/Elev= 30
  4542.0 1042.08  4610.9 1039.44  4631.9 1037.88  4647.0 1038.16  4719.2 1035.17
  4761.3 1032.80  4842.6 1030.45  4863.7 1028.89  4869.7 1029.39  4878.5 1027.49
  4884.7 1028.57  4890.7 1027.16  4899.8 1027.64  4905.8 1025.86  4920.8 1026.27
  4924.8 1024.87  4925.1 1024.37  4928.8 1024.87  4986.4 1025.95  5022.4 1025.25
  5029.2 1026.45  5053.1 1028.38  5058.4 1027.63  5115.4 1028.69  5163.5 1030.42
  5171.7 1031.50  5177.0 1030.97  5216.5 1032.74  5238.9 1034.62  5280.1 1035.03
#Mann=4,-1,0
  4542.0    0.05       0  4924.8    0.03       0  4928.8    0.05       0
  5115.4    0.12       0
Bank Sta=4924.8,4928.8
Exp/Cntr=0.3,0.1

Type RM Length L Ch R = 1,3228,198,198,198
BEGIN DESCRIPTION:
Mapping XS 2fb70498
END DESCRIPTION:
XS GIS Cut Line= 4
      2828071.87     10248334.39      2827803.21     10248090.34
      2827651.43     10247989.84      2827393.03     10247639.15
#Sta/Elev= 30
  4544.3 1038.49  4762.0 1031.17  4776.1 1031.89  4782.9 1030.80  4818.7 1029.55
  4952.9 1027.09  4976.3 1025.33  4989.0 1022.61  4998.1 1022.49  5002.0 1021.03
  5002.3 1020.53  5006.0 1021.03  5019.1 1023.12  5024.7 1022.90  5034.2 1022.54
  5055.2 1025.55  5070.3 1025.77  5111.8 1025.22  5147.3 1022.12  5172.6 1022.40
  5191.3 1025.18  5220.5 1027.95  5226.7 1027.72  5241.4 1028.80  5247.6 1028.04
  5276.9 1028.19  5412.6 1031.05  5441.9 1033.40  5448.1 1034.48  5524.9 1038.84
#Mann=5,-1,0
  4544.3    0.05       0  5002.0    0.03       0  5006.0    0.05       0
  5024.7    0.12       0  5172.6    0.05       0
Bank Sta=5002,5006
Exp/Cntr=0.3,0.1

Type RM Length L Ch R = 1,3030,240,240,240
BEGIN DESCRIPTION:
Mapping XS bfa76f83
END DESCRIPTION:
XS GIS Cut Line= 4
      2828203.13     10248244.14      2827899.61     10247952.92
      2827655.54     10247733.46      2827434.06     10247524.29
#Sta/Elev= 30
  4446.3 1036.33  4692.6 1029.25  4706.8 1029.73  4720.9 1028.35  4756.4 1027.95
  4763.4 1027.17  4904.9 1025.44  4940.1 1024.48  4961.7 1021.81  4975.9 1021.10
  5004.3 1021.54  5015.8 1021.06  5016.3 1020.56  5020.8 1020.56  5021.2 1021.06
  5053.7 1023.45  5067.9 1025.29  5096.3 1026.40  5103.0 1025.29  5110.5 1025.99
  5117.2 1025.46  5237.6 1030.79  5336.7 1033.86  5350.9 1034.20  5358.1 1033.70
  5365.0 1034.85  5372.3 1034.54  5400.6 1035.65  5428.8 1038.08  5499.8 1041.25
#Mann=3,-1,0
  4446.3    0.05       0  5015.8    0.03       0  5021.2    0.05       0
Bank Sta=5015.8,5021.2
Exp/Cntr=0.3,0.1

Type RM Length L Ch R = 1,2790,871,871,871
BEGIN DESCRIPTION:
Mapping XS b07f20f4
END DESCRIPTION:
XS GIS Cut Line= 2
      2828273.66     10247999.97      2827687.72     10247424.89
#Sta/Elev= 30
  4590.7 1029.09  4679.0 1027.87  4700.1 1027.06  4735.6 1027.04  4756.7 1025.63
  4778.0 1026.10  4785.0 1024.93  4820.4 1023.68  4855.7 1023.50  4884.0 1024.42
  4947.7 1023.68  4990.1 1021.22  5004.3 1019.05  5011.3 1019.88  5046.7 1019.21
  5051.0 1018.47  5051.5 1017.97  5056.0 1017.97  5056.4 1018.47  5075.0 1018.63
  5082.0 1019.26  5110.3 1025.17  5117.4 1025.13  5138.6 1026.72  5195.2 1028.12
  5322.5 1033.94  5350.7 1034.42  5357.9 1035.14  5364.9 1034.71  5411.7 1036.76
#Mann=3,-1,0
  4590.7    0.05       0  5051.0    0.05       0  5056.4    0.05       0
Bank Sta=5051,5056.4
Exp/Cntr=0.3,0.1

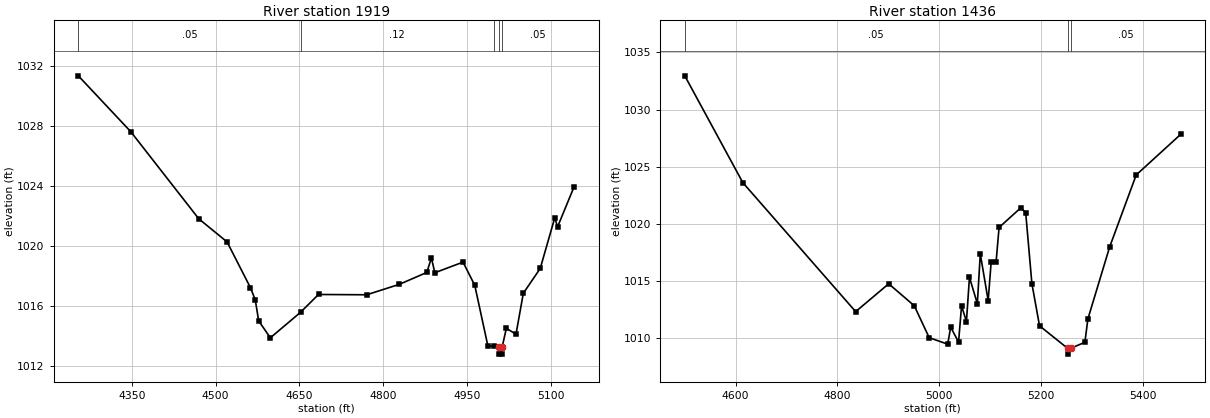
Type RM Length L Ch R = 1,1919,483,483,483
BEGIN DESCRIPTION:
LITTLE LLANO 047 2.0
END DESCRIPTION:
XS GIS Cut Line= 3
      2829105.72     10247603.14      2828496.00     10247174.00
      2828355.65     10247153.11
#Sta/Elev= 30
  4254.4 1031.34  4348.1 1027.62  4470.0 1021.80  4520.6 1020.26  4562.4 1017.21
  4571.1 1016.39  4577.2 1014.99  4598.1 1013.86  4652.1 1015.56  4684.3 1016.75
  4770.6 1016.73  4829.2 1017.43  4878.1 1018.22  4886.4 1019.19  4892.5 1018.20
  4943.0 1018.91  4964.0 1017.36  4987.4 1013.33  4997.9 1013.28  5007.7 1013.27
  5008.1 1012.77  5012.7 1012.77  5013.2 1013.27  5020.5 1014.49  5037.8 1014.10
  5050.9 1016.83  5081.2 1018.49  5107.2 1021.87  5112.2 1021.26  5141.9 1023.95
#Mann=5,-1,0
  4254.4    0.05       0  4652.1    0.12       0  4997.9    0.05       0
  5007.7    0.05       0  5013.2    0.05       0
Bank Sta=5007.7,5013.2
Exp/Cntr=0.3,0.1

Type RM Length L Ch R = 1,1436,0,0,0
BEGIN DESCRIPTION:
LITTLE LLANO 047 1.0
END DESCRIPTION:
XS GIS Cut Line= 3
      2829205.68     10247453.11      2828911.75     10247049.00
      2828505.69     10246803.12
#Sta/Elev= 30
  4500.3 1032.95  4614.3 1023.60  4836.1 1012.30  4901.0 1014.74  4951.2 1012.82
  4980.6 1010.02  5017.0 1009.45  5022.8 1010.94  5038.3 1009.64  5044.2 1012.81
  5053.8 1011.43  5059.7 1015.31  5075.2 1013.00  5081.0 1017.36  5096.5 1013.27
  5102.4 1016.66  5112.0 1016.62  5117.9 1019.67  5160.5 1021.39  5170.2 1020.98
  5182.4 1014.76  5197.4 1011.06  5252.8 1009.08  5253.3 1008.58  5258.3 1009.08
  5286.6 1009.62  5292.4 1011.65  5335.1 1017.95  5387.4 1024.27  5474.7 1027.82
#Mann=3,-1,0
  4500.3    0.05       0  5252.8    0.05       0  5258.3    0.05       0
Bank Sta=5252.8,5258.3
Exp/Cntr=0.3,0.1

Chan Stop Cuts=-1