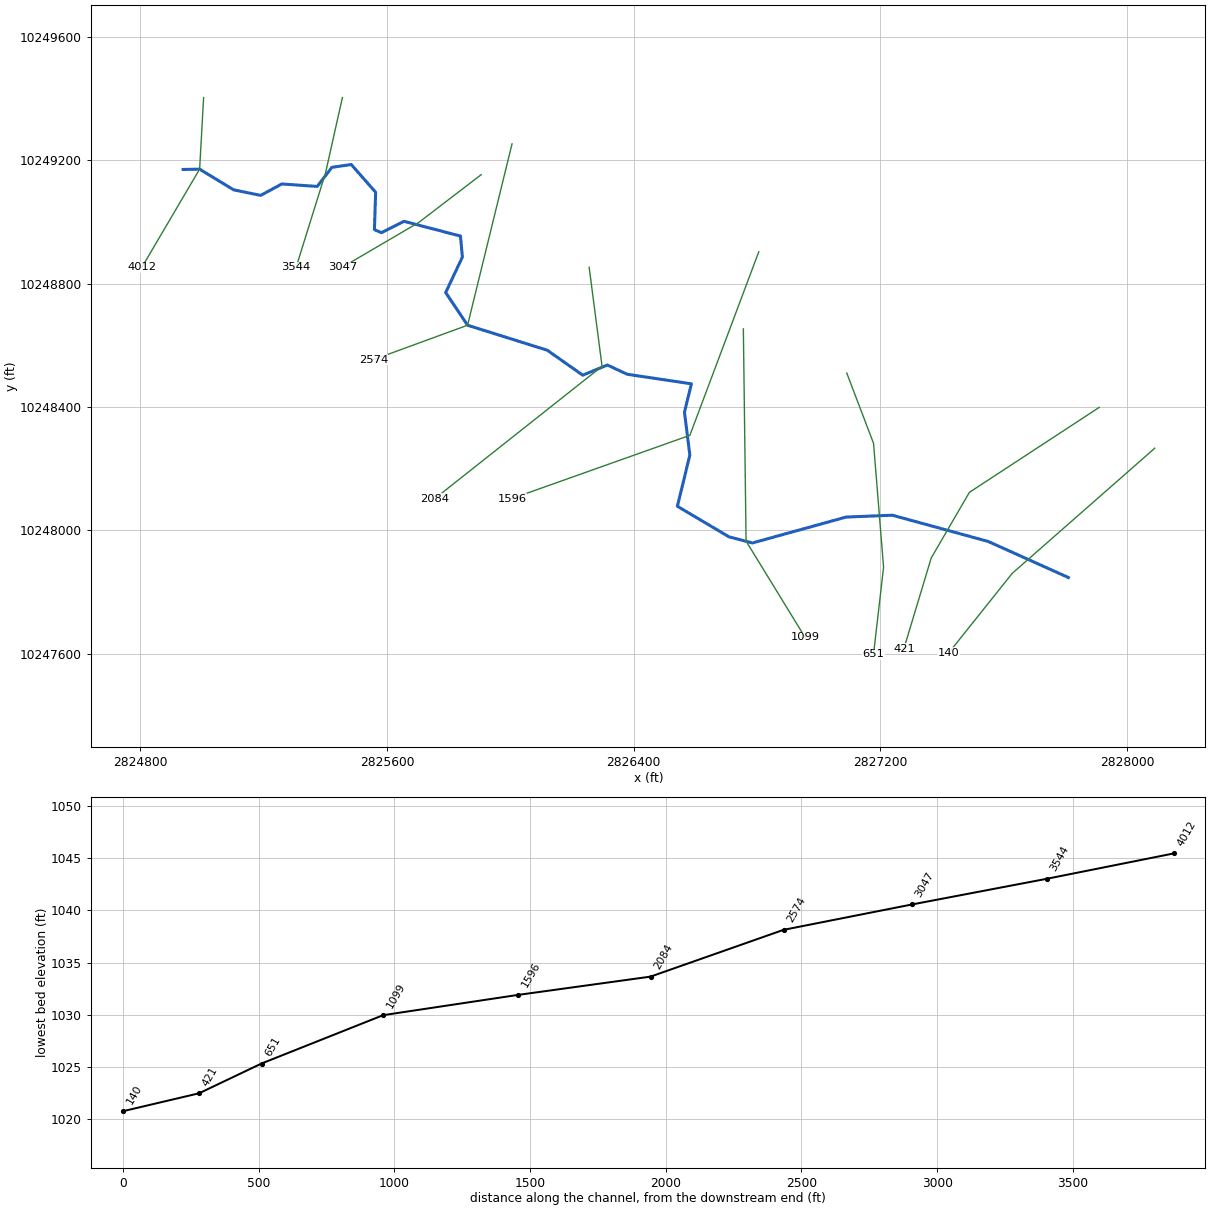
--- LITTLE LLANO 048.prj (project) ---

Proj Title=LITTLE LLANO 048 Base Level Engineering
Current Plan=p01
Default Exp/Contr=0.3,0.1
English Units
Geom File=g01
Flow File=f01
Plan File=p01
BEGIN DESCRIPTION:
LITTLE LLANO 048
END DESCRIPTION:

--- LITTLE LLANO 048.p01 (plan) ---

Plan Title=Multiple Run
Short Identifier=Multiple
Geom File=g01
Flow File=f01
Subcritical Flow
K Sum by GR= 0
Std Step Tol= 0.01
Critical Tol= 0.01
Num of Std Step Trials= 20
Max Error Tol= 0.3
Flow Tol Ratio= 0.001
Split Flow NTrial= 30
Split Flow Tol= 0.02
Split Flow Ratio= 0.02
Log Output Level= 0
Friction Slope Method= 1
Unsteady Friction Slope Method= 2
Unsteady Bridges Friction Slope Method= 1
Parabolic Critical Depth
Global Vel Dist=  1 , 1 , 1
Global Log Level= 0
CheckData=True
Encroach Param= -1, 0, 0, 0
BEGIN DESCRIPTION:
Multiple Run
END DESCRIPTION:

--- LITTLE LLANO 048.f01 (steady flow) ---

Flow Title=Multiple
Number of Profiles=7
Profile Names=10-year,25-year,50-year,1pct_min,100-year,1pct_plu,500-year
River Rch & RM= LITTLE LLANO 048,Reach-1,4012
     331     526     547     403     701    1219     935
Boundary for River Rch & Prof#=LITTLE LLANO 048,Reach-1,1
Up Type=0
Dn Type=3
Dn Slope=0.005
Boundary for River Rch & Prof#=LITTLE LLANO 048,Reach-1,2
Up Type=0
Dn Type=3
Dn Slope=0.005
Boundary for River Rch & Prof#=LITTLE LLANO 048,Reach-1,3
Up Type=0
Dn Type=3
Dn Slope=0.005
Boundary for River Rch & Prof#=LITTLE LLANO 048,Reach-1,4
Up Type=0
Dn Type=3
Dn Slope=0.005
Boundary for River Rch & Prof#=LITTLE LLANO 048,Reach-1,5
Up Type=0
Dn Type=3
Dn Slope=0.005
Boundary for River Rch & Prof#=LITTLE LLANO 048,Reach-1,6
Up Type=0
Dn Type=3
Dn Slope=0.005
Boundary for River Rch & Prof#=LITTLE LLANO 048,Reach-1,7
Up Type=0
Dn Type=3
Dn Slope=0.005

--- LITTLE LLANO 048.g01 (geometry) ---

Geom Title=Existing Conditions

River Reach=LITTLE LLANO 048,Reach-1
Reach XY= 30
      2824939.25     10249170.00      2824992.75     10249171.00
      2825103.00     10249104.00      2825190.75     10249086.00
      2825259.25     10249123.00      2825374.00     10249115.00
      2825421.75     10249177.00      2825484.50     10249186.00
      2825563.50     10249096.00      2825559.50     10248975.00
      2825582.25     10248965.00      2825655.25     10249002.00
      2825838.50     10248954.00      2825844.75     10248886.00
      2825790.50     10248771.00      2825861.50     10248665.00
      2826119.75     10248584.00      2826235.00     10248503.00
      2826314.75     10248536.00      2826379.00     10248506.00
      2826587.25     10248475.00      2826564.75     10248383.00
      2826582.25     10248244.00      2826541.75     10248078.00
      2826709.00     10247979.00      2826785.00     10247959.00
      2827088.75     10248043.00      2827238.75     10248049.00
      2827549.25     10247964.00      2827809.50     10247847.00

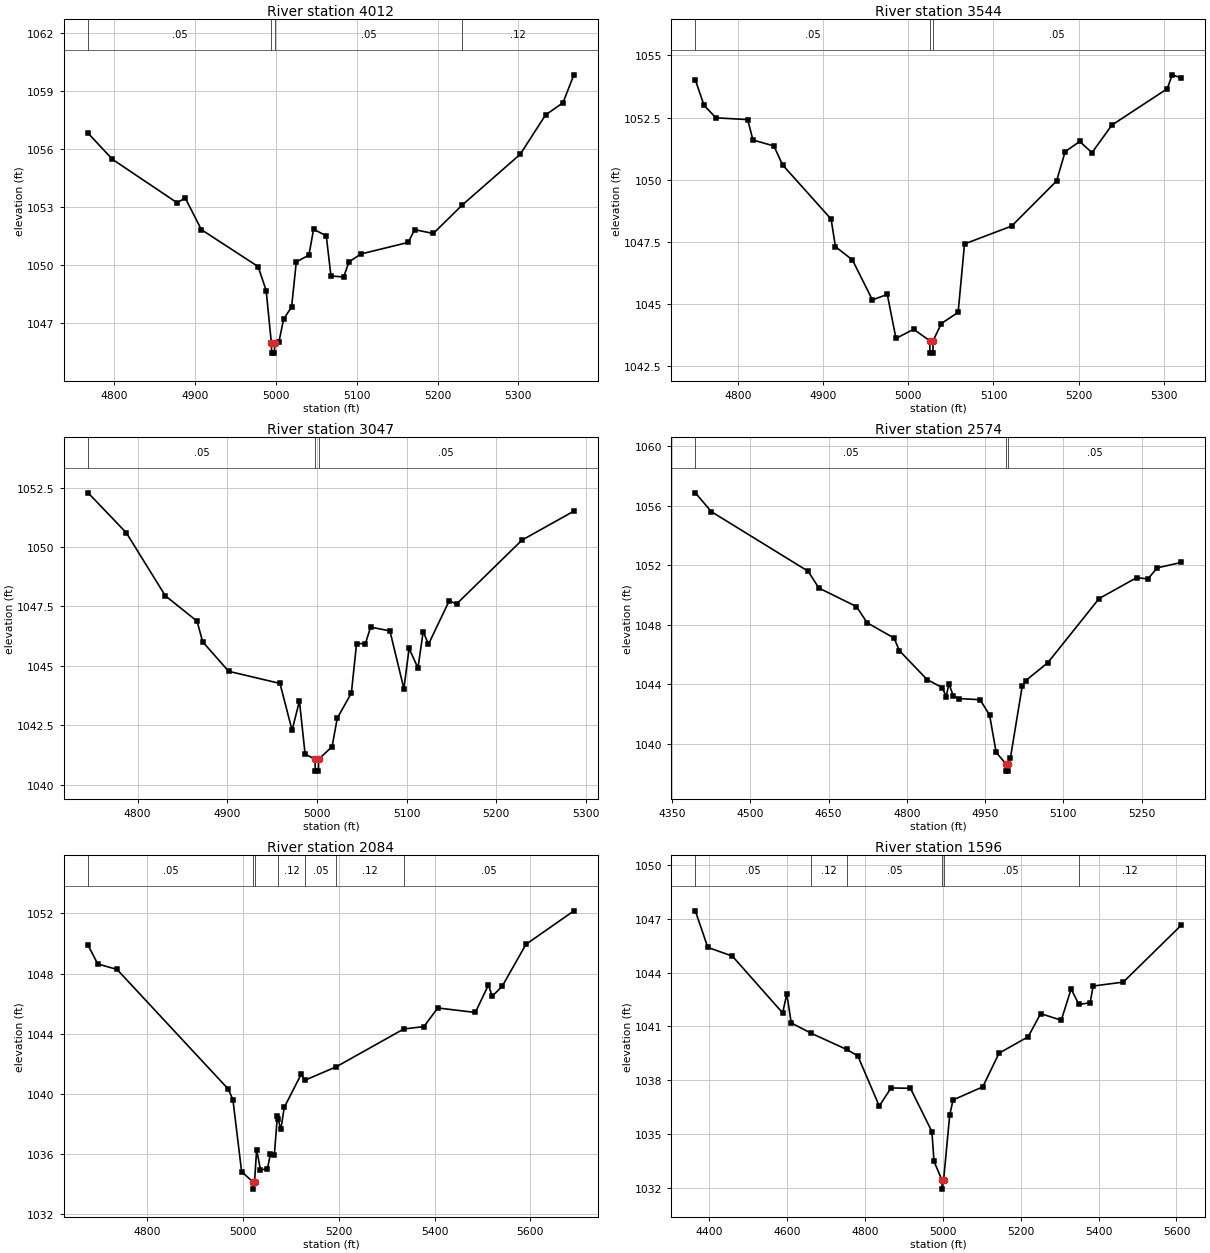
Type RM Length L Ch R = 1,4012,468,468,468
BEGIN DESCRIPTION:
LITTLE LLANO 048 8.0
END DESCRIPTION:
XS GIS Cut Line= 3
      2825005.69     10249403.14      2824992.75     10249171.00
      2824805.71     10248853.15
#Sta/Elev= 30
  4767.5 1056.84  4797.6 1055.49  4877.7 1053.24  4887.7 1053.49  4907.7 1051.85
  4977.9 1049.94  4987.9 1048.70  4994.4 1045.96  4994.7 1045.46  4998.2 1045.46
  4998.4 1045.96  5003.7 1046.04  5009.5 1047.22  5019.4 1047.85  5025.2 1050.18
  5040.8 1050.53  5046.6 1051.87  5062.3 1051.53  5068.1 1049.45  5083.8 1049.40
  5090.4 1050.18  5105.2 1050.59  5163.8 1051.19  5171.6 1051.85  5194.8 1051.65
  5230.5 1053.12  5302.4 1055.75  5333.8 1057.79  5355.2 1058.41  5368.8 1059.86
#Mann=4,-1,0
  4767.5    0.05       0  4994.4    0.03       0  4998.4    0.05       0
  5230.5    0.12       0
Bank Sta=4994.4,4998.4
Exp/Cntr=0.3,0.1

Type RM Length L Ch R = 1,3544,497,497,497
BEGIN DESCRIPTION:
LITTLE LLANO 048 7.0
END DESCRIPTION:
XS GIS Cut Line= 3
      2825455.69     10249403.15      2825401.00     10249159.00
      2825305.68     10248853.11
#Sta/Elev= 30
  4749.8 1054.02  4760.1 1052.99  4774.1 1052.49  4811.3 1052.42  4817.5 1051.60
  4842.1 1051.36  4852.3 1050.60  4909.3 1048.42  4914.4 1047.31  4934.3 1046.78
  4957.8 1045.17  4975.3 1045.39  4985.5 1043.62  5006.2 1043.99  5025.1 1043.53
  5025.4 1043.03  5028.9 1043.03  5029.1 1043.53  5038.8 1044.22  5058.5 1044.67
  5066.0 1047.42  5121.4 1048.14  5174.1 1049.95  5184.2 1051.13  5201.3 1051.54
  5215.7 1051.09  5239.1 1052.20  5304.1 1053.66  5309.9 1054.22  5320.4 1054.10
#Mann=3,-1,0
  4749.8    0.05       0  5025.1    0.03       0  5029.1    0.05       0
Bank Sta=5025.1,5029.1
Exp/Cntr=0.3,0.1

Type RM Length L Ch R = 1,3047,473,473,473
BEGIN DESCRIPTION:
LITTLE LLANO 048 6.0
END DESCRIPTION:
XS GIS Cut Line= 3
      2825905.66     10249153.10      2825703.00     10248998.00
      2825455.71     10248853.13
#Sta/Elev= 30
  4744.8 1052.28  4787.4 1050.60  4830.9 1047.95  4866.3 1046.88  4872.6 1046.01
  4901.6 1044.77  4958.8 1044.26  4972.3 1042.29  4980.5 1043.52  4986.8 1041.29
  4997.9 1041.07  4998.2 1040.57  5001.7 1040.57  5001.9 1041.07  5016.9 1041.60
  5022.7 1042.80  5038.4 1043.85  5044.2 1045.93  5054.1 1045.94  5059.9 1046.63
  5081.4 1046.47  5097.0 1044.04  5102.8 1045.73  5112.7 1044.91  5118.5 1046.44
  5124.4 1045.91  5147.6 1047.74  5155.7 1047.60  5228.7 1050.29  5286.6 1051.51
#Mann=3,-1,0
  4744.8    0.05       0  4997.9    0.03       0  5001.9    0.05       0
Bank Sta=4997.9,5001.9
Exp/Cntr=0.3,0.1

Type RM Length L Ch R = 1,2574,490,490,490
BEGIN DESCRIPTION:
LITTLE LLANO 048 5.0
END DESCRIPTION:
XS GIS Cut Line= 3
      2826005.68     10249253.08      2825861.50     10248665.00
      2825555.72     10248553.13
#Sta/Elev= 30
  4394.5 1056.88  4425.4 1055.61  4610.7 1051.60  4631.3 1050.47  4703.4 1049.22
  4723.9 1048.13  4775.4 1047.10  4785.7 1046.25  4838.9 1044.30  4868.1 1043.76
  4875.3 1043.14  4880.5 1044.03  4888.7 1043.23  4899.0 1043.03  4940.2 1042.95
  4958.5 1041.92  4971.1 1039.40  4989.6 1038.64  4989.9 1038.14  4993.4 1038.14
  4993.6 1038.64  4998.4 1039.02  5021.1 1043.87  5027.5 1044.23  5070.1 1045.44
  5168.4 1049.76  5240.5 1051.17  5261.8 1051.08  5279.9 1051.83  5325.6 1052.19
#Mann=3,-1,0
  4394.5    0.05       0  4989.6    0.03       0  4993.6    0.05       0
Bank Sta=4989.6,4993.6
Exp/Cntr=0.3,0.1

Type RM Length L Ch R = 1,2084,488,488,488
BEGIN DESCRIPTION:
LITTLE LLANO 048 4.0
END DESCRIPTION:
XS GIS Cut Line= 3
      2826255.69     10248853.09      2826297.50     10248532.00
      2825755.70     10248103.12
#Sta/Elev= 30
  4676.2 1049.88  4696.3 1048.64  4736.7 1048.27  4968.6 1040.33  4978.7 1039.62
  4996.9 1034.82  5019.9 1034.16  5020.2 1033.66  5023.9 1034.16  5028.3 1036.29
  5036.3 1034.94  5050.8 1035.01  5057.2 1036.01  5065.2 1035.92  5071.6 1038.50
  5073.0 1038.33  5078.8 1037.63  5086.0 1039.10  5121.3 1041.30  5128.9 1040.90
  5194.8 1041.80  5335.5 1044.31  5377.7 1044.47  5406.6 1045.71  5485.1 1045.41
  5512.5 1047.24  5520.3 1046.49  5541.2 1047.15  5590.8 1049.94  5691.0 1052.17
#Mann=7,-1,0
  4676.2    0.05       0  5019.9    0.05       0  5023.9    0.05       0
  5073.0    0.12       0  5128.9    0.05       0  5194.8    0.12       0
  5335.5    0.05       0
Bank Sta=5019.9,5023.9
Exp/Cntr=0.3,0.1

Type RM Length L Ch R = 1,1596,497,497,497
BEGIN DESCRIPTION:
LITTLE LLANO 048 3.0
END DESCRIPTION:
XS GIS Cut Line= 3
      2826805.69     10248903.14      2826582.25     10248308.00
      2826005.67     10248103.11
#Sta/Elev= 30
  4364.3 1047.45  4396.4 1045.41  4459.5 1044.92  4588.6 1041.75  4599.3 1042.80
  4610.7 1041.19  4661.2 1040.62  4752.9 1039.71  4781.6 1039.35  4836.7 1036.55
  4867.0 1037.56  4916.8 1037.54  4971.9 1035.12  4977.3 1033.46  4997.9 1032.41
  4998.2 1031.91  5001.9 1032.41  5017.6 1036.04  5026.2 1036.89  5102.5 1037.62
  5144.3 1039.50  5219.2 1040.42  5251.1 1041.71  5304.1 1041.34  5329.4 1043.09
  5349.4 1042.22  5378.4 1042.32  5385.8 1043.25  5463.3 1043.47  5611.9 1046.64
#Mann=6,-1,0
  4364.3    0.05       0  4661.2    0.12       0  4752.9    0.05       0
  4997.9    0.05       0  5001.9    0.05       0  5349.4    0.12       0
Bank Sta=4997.9,5001.9
Exp/Cntr=0.3,0.1

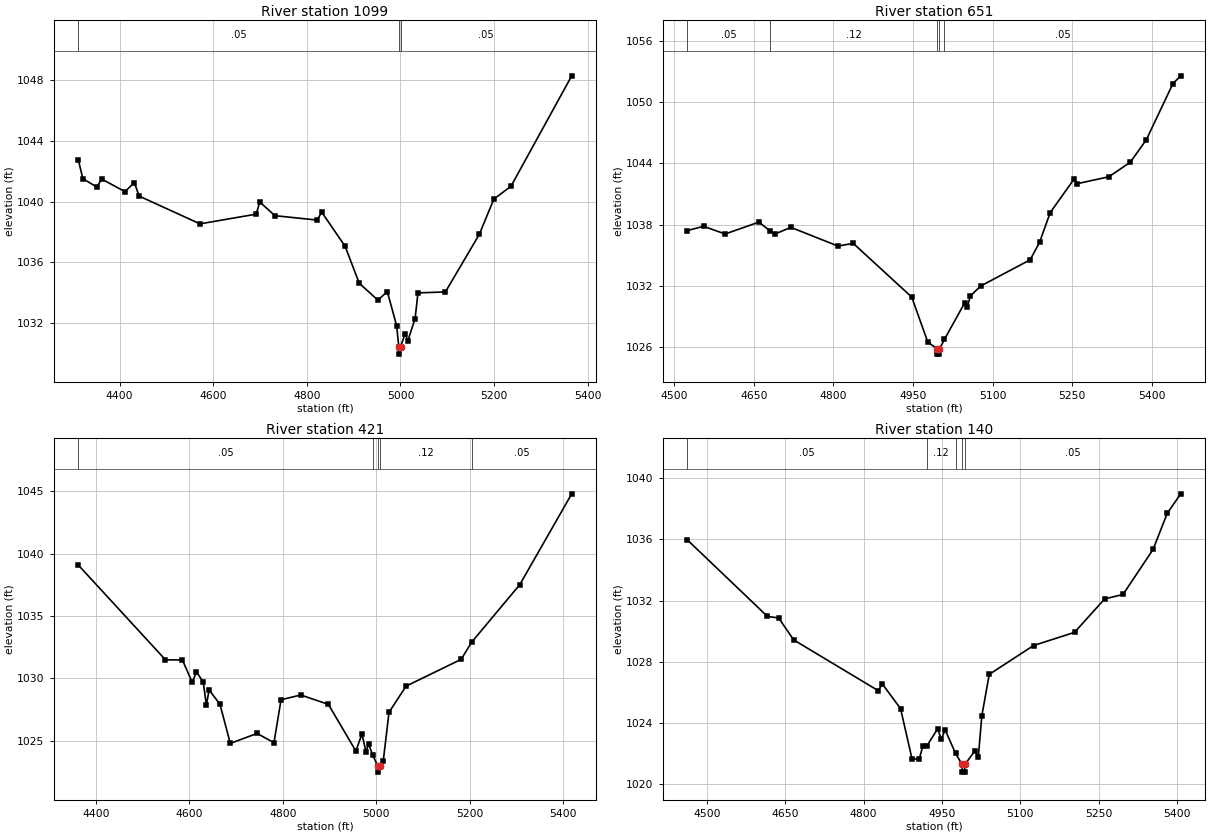
Type RM Length L Ch R = 1,1099,448,448,448
BEGIN DESCRIPTION:
LITTLE LLANO 048 2.0
END DESCRIPTION:
XS GIS Cut Line= 3
      2826755.68     10248653.14      2826764.50     10247965.00
      2826955.67     10247653.13
#Sta/Elev= 30
  4311.8 1042.77  4321.8 1041.51  4351.8 1040.96  4361.8 1041.49  4411.8 1040.66
  4431.8 1041.26  4441.8 1040.37  4571.9 1038.54  4691.9 1039.18  4699.5 1039.98
  4731.9 1039.08  4821.9 1038.79  4831.9 1039.31  4881.9 1037.06  4911.9 1034.64
  4951.9 1033.52  4971.9 1034.09  4991.9 1031.83  4996.4 1030.47  4996.7 1029.97
  5000.4 1030.47  5010.0 1031.32  5015.8 1030.85  5031.3 1032.31  5037.4 1034.00
  5096.0 1034.06  5168.6 1037.86  5199.5 1040.17  5236.2 1041.02  5365.8 1048.28
#Mann=3,-1,0
  4311.8    0.05       0  4996.4    0.05       0  5000.4    0.05       0
Bank Sta=4996.4,5000.4
Exp/Cntr=0.3,0.1

Type RM Length L Ch R = 1,651,230,230,230
BEGIN DESCRIPTION:
Mapping XS 68fc8ce8
END DESCRIPTION:
XS GIS Cut Line= 4
      2827090.94     10248509.97      2827177.75     10248282.10
      2827210.30     10247880.62      2827177.75     10247598.53
#Sta/Elev= 30
  4524.3 1037.43  4555.0 1037.85  4595.8 1037.10  4659.4 1038.26  4679.7 1037.44
  4689.5 1037.09  4719.6 1037.75  4808.4 1035.92  4837.4 1036.18  4947.7 1030.92
  4977.8 1026.53  4995.9 1025.84  4996.1 1025.34  4999.6 1025.34  4999.9 1025.84
  5009.4 1026.79  5047.5 1030.36  5052.5 1029.95  5058.1 1031.04  5078.1 1032.02
  5170.9 1034.57  5188.6 1036.27  5208.7 1039.19  5254.4 1042.52  5259.4 1042.02
  5319.4 1042.70  5359.7 1044.12  5389.9 1046.31  5440.2 1051.82  5454.9 1052.58
#Mann=5,-1,0
  4524.3    0.05       0  4679.7    0.12       0  4995.9    0.07       0
  4999.9    0.12       0  5009.4    0.05       0
Bank Sta=4995.9,4999.9
Exp/Cntr=0.3,0.1

Type RM Length L Ch R = 1,421,281,281,281
BEGIN DESCRIPTION:
Mapping XS 35629f99
END DESCRIPTION:
XS GIS Cut Line= 4
      2827909.48     10248398.65      2827488.49     10248123.06
      2827364.79     10247910.38      2827276.24     10247616.64
#Sta/Elev= 30
  4362.0 1039.09  4548.7 1031.49  4584.9 1031.48  4605.9 1029.69  4615.1 1030.51
  4629.5 1029.72  4636.2 1027.86  4642.1 1029.07  4665.3 1027.93  4687.4 1024.79
  4744.7 1025.59  4780.9 1024.85  4796.0 1028.29  4838.2 1028.67  4897.3 1027.92
  4956.1 1024.18  4969.2 1025.55  4977.6 1024.13  4983.4 1024.73  4992.0 1023.88
  5002.9 1022.99  5003.1 1022.49  5006.9 1022.99  5014.8 1023.42  5027.1 1027.29
  5063.6 1029.38  5181.5 1031.53  5203.6 1032.89  5306.8 1037.51  5418.0 1044.79
#Mann=5,-1,0
  4362.0    0.05       0  4992.0    0.12       0  5002.9    0.07       0
  5006.9    0.12       0  5203.6    0.05       0
Bank Sta=5002.9,5006.9
Exp/Cntr=0.3,0.1

Type RM Length L Ch R = 1,140,0,0,0
BEGIN DESCRIPTION:
LITTLE LLANO 048 1.0
END DESCRIPTION:
XS GIS Cut Line= 3
      2828089.59     10248266.26      2827627.38     10247860.47
      2827421.22     10247602.23
#Sta/Elev= 30
  4462.0 1035.98  4615.5 1030.97  4637.3 1030.86  4665.8 1029.43  4828.1 1026.10
  4835.6 1026.55  4870.7 1024.93  4892.6 1021.65  4906.3 1021.61  4913.4 1022.47
  4921.4 1022.50  4941.9 1023.62  4948.6 1022.91  4956.1 1023.54  4976.0 1022.00
  4988.6 1021.27  4989.0 1020.77  4993.5 1020.77  4994.0 1021.27  5012.8 1022.15
  5019.7 1021.77  5026.4 1024.45  5040.6 1027.17  5125.6 1029.06  5204.0 1029.92
  5261.7 1032.11  5296.9 1032.40  5354.5 1035.35  5381.7 1037.72  5407.5 1038.99
#Mann=5,-1,0
  4462.0    0.05       0  4921.4    0.12       0  4976.0    0.05       0
  4988.6    0.05       0  4994.0    0.05       0
Bank Sta=4988.6,4994
Exp/Cntr=0.3,0.1

Chan Stop Cuts=-1