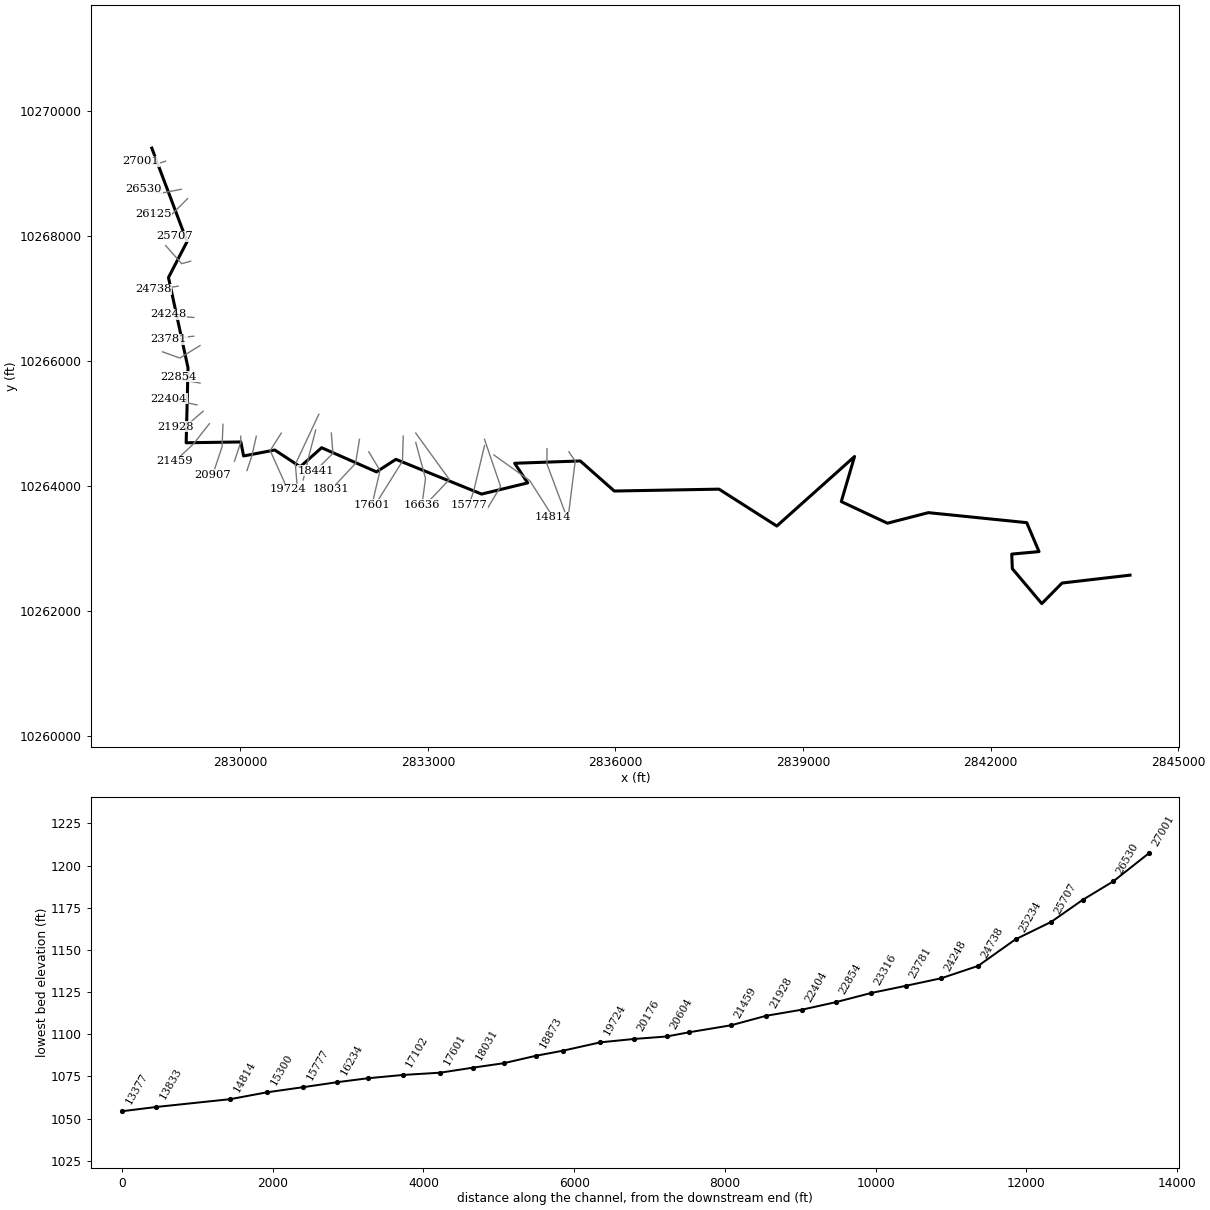
--- LITTLE LLANO 052.prj (project) ---

Proj Title=LITTLE LLANO 052 Base Level Engineering
Current Plan=p01
Default Exp/Contr=0.3,0.1
English Units
Geom File=g01
Flow File=f01
Plan File=p01
BEGIN DESCRIPTION:
LITTLE LLANO 052
END DESCRIPTION:

--- LITTLE LLANO 052.p01 (plan) ---

Plan Title=Multiple Run
Short Identifier=Multiple
Geom File=g01
Flow File=f01
Subcritical Flow
K Sum by GR= 0
Std Step Tol= 0.01
Critical Tol= 0.01
Num of Std Step Trials= 20
Max Error Tol= 0.3
Flow Tol Ratio= 0.001
Split Flow NTrial= 30
Split Flow Tol= 0.02
Split Flow Ratio= 0.02
Log Output Level= 0
Friction Slope Method= 1
Unsteady Friction Slope Method= 2
Unsteady Bridges Friction Slope Method= 1
Parabolic Critical Depth
Global Vel Dist=  1 , 1 , 1
Global Log Level= 0
CheckData=True
Encroach Param= -1, 0, 0, 0
BEGIN DESCRIPTION:
Multiple Run
END DESCRIPTION:

--- LITTLE LLANO 052.f01 (steady flow) ---

Flow Title=Multiple
Number of Profiles=7
Profile Names=10-year,25-year,50-year,1pct_min,100-year,1pct_plu,500-year
River Rch & RM= LITTLE LLANO 052,Reach-1,27001
     410     658    1175     949    1615    2749    2294
River Rch & RM= LITTLE LLANO 052,Reach-1,19230
     721    1206    1991    1474    2762    5177    3875
River Rch & RM= LITTLE LLANO 052,Reach-1,12839
    1102    1907    2886    1983    4025    8170    5600
River Rch & RM= LITTLE LLANO 052,Reach-1,3823
    1271    2223    3290    2216    4600    9551    6384
Boundary for River Rch & Prof#=LITTLE LLANO 052,Reach-1,1
Up Type=0
Dn Type=3
Dn Slope=0.005
Boundary for River Rch & Prof#=LITTLE LLANO 052,Reach-1,2
Up Type=0
Dn Type=3
Dn Slope=0.005
Boundary for River Rch & Prof#=LITTLE LLANO 052,Reach-1,3
Up Type=0
Dn Type=3
Dn Slope=0.005
Boundary for River Rch & Prof#=LITTLE LLANO 052,Reach-1,4
Up Type=0
Dn Type=3
Dn Slope=0.005
Boundary for River Rch & Prof#=LITTLE LLANO 052,Reach-1,5
Up Type=0
Dn Type=3
Dn Slope=0.005
Boundary for River Rch & Prof#=LITTLE LLANO 052,Reach-1,6
Up Type=0
Dn Type=3
Dn Slope=0.005
Boundary for River Rch & Prof#=LITTLE LLANO 052,Reach-1,7
Up Type=0
Dn Type=3
Dn Slope=0.005

--- LITTLE LLANO 052.g01 (geometry) ---

Geom Title=Existing Conditions

River Reach=LITTLE LLANO 052,Reach-1
Reach XY= 30
      2828584.50     10269412.00      2829148.25     10267916.00
      2828851.00     10267342.00      2829163.50     10265897.00
      2829134.00     10264698.00      2830009.00     10264711.00
      2830052.00     10264487.00      2830552.00     10264582.00
      2830958.25     10264314.00      2831300.50     10264619.00
      2832178.25     10264232.00      2832488.00     10264433.00
      2833859.25     10263877.00      2834596.25     10264056.00
      2834387.75     10264370.00      2835437.25     10264407.00
      2835981.50     10263926.00      2837656.00     10263956.00
      2838580.50     10263366.00      2839824.00     10264478.00
      2839611.75     10263757.00      2840350.00     10263411.00
      2841005.00     10263580.00      2842578.00     10263420.00
      2842774.50     10262957.00      2842338.25     10262917.00
      2842347.50     10262684.00      2842818.75     10262125.00
      2843143.00     10262454.00      2844230.00     10262580.00

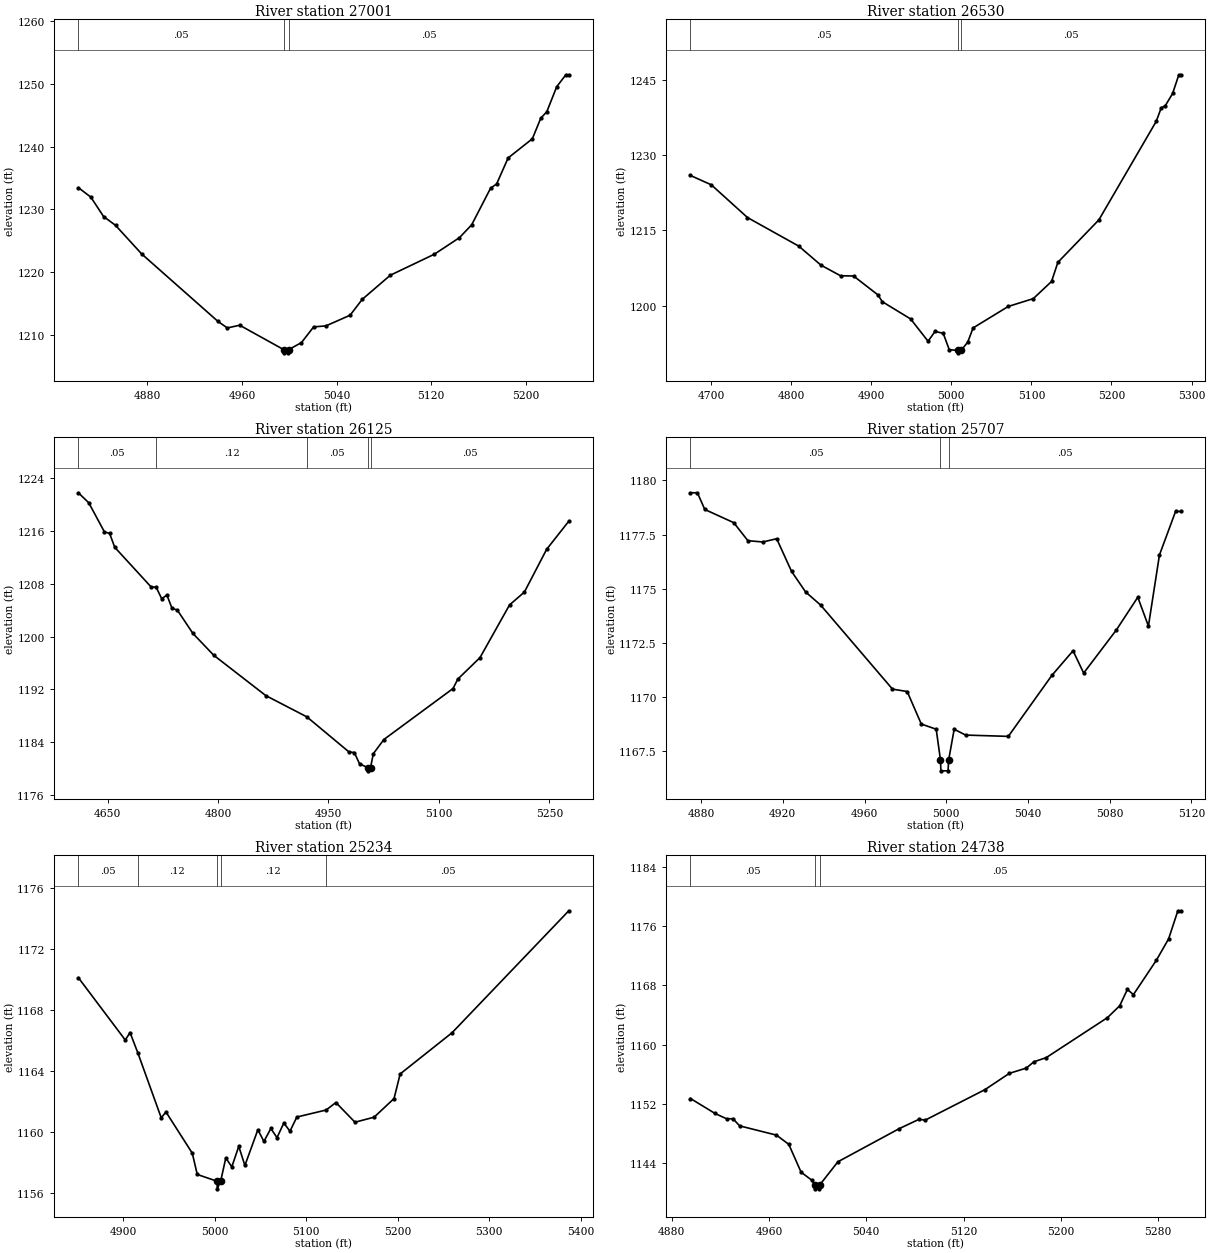
Type RM Length L Ch R = 1,27001,471,471,471
BEGIN DESCRIPTION:
LITTLE LLANO 052 54.0
END DESCRIPTION:
XS GIS Cut Line= 3
      2828805.64     10269203.10      2828635.75     10269149.00
      2828405.73     10269203.10
#Sta/Elev= 30
  4821.7 1233.46  4832.2 1231.96  4843.0 1228.87  4853.1 1227.47  4875.2 1222.92
  4939.7 1212.19  4947.6 1211.15  4958.1 1211.58  4995.4 1207.69  4995.7 1207.19
  4999.2 1207.19  4999.4 1207.69  5010.3 1208.82  5020.6 1211.32  5030.9 1211.47
  5051.4 1213.17  5061.7 1215.70  5085.4 1219.53  5122.7 1222.88  5143.9 1225.51
  5154.2 1227.55  5170.2 1233.38  5175.3 1234.05  5185.0 1238.18  5205.5 1241.23
  5212.6 1244.50  5217.7 1245.53  5226.1 1249.51  5233.8 1251.41  5236.3 1251.41
#Mann=3,-1,0
  4821.7    0.05       0  4995.4    0.03       0  4999.4    0.05       0
Bank Sta=4995.4,4999.4
Exp/Cntr=0.3,0.1

Type RM Length L Ch R = 1,26530,405,405,405
BEGIN DESCRIPTION:
LITTLE LLANO 052 53.0
END DESCRIPTION:
XS GIS Cut Line= 3
      2829055.67     10268753.11      2828735.75     10268692.00
      2828455.64     10268753.12
#Sta/Elev= 30
  4674.3 1225.92  4700.3 1224.06  4745.5 1217.54  4809.6 1211.84  4837.2 1208.06
  4861.7 1205.94  4877.9 1205.90  4908.4 1202.13  4913.8 1200.78  4949.2 1197.34
  4971.0 1192.90  4979.7 1194.86  4989.9 1194.48  4997.5 1191.19  5008.3 1191.09
  5008.6 1190.59  5012.3 1191.09  5020.5 1192.72  5027.2 1195.55  5071.1 1199.83
  5102.4 1201.39  5125.2 1204.81  5133.1 1208.62  5184.3 1217.08  5255.9 1236.70
  5262.1 1239.37  5267.3 1239.84  5276.4 1242.26  5284.1 1245.98  5286.7 1245.98
#Mann=3,-1,0
  4674.3    0.05       0  5008.3    0.03       0  5012.3    0.05       0
Bank Sta=5008.3,5012.3
Exp/Cntr=0.3,0.1

Type RM Length L Ch R = 1,26125,418,418,418
BEGIN DESCRIPTION:
LITTLE LLANO 052 52.0
END DESCRIPTION:
XS GIS Cut Line= 3
      2829155.65     10268603.08      2828880.75     10268327.00
      2828605.69     10268353.11
#Sta/Elev= 30
  4610.4 1221.83  4624.5 1220.31  4645.7 1215.91  4652.8 1215.66  4659.8 1213.56
  4709.3 1207.53  4715.9 1207.53  4723.5 1205.77  4730.6 1206.31  4737.6 1204.30
  4744.7 1204.05  4765.9 1200.50  4794.2 1197.19  4864.9 1191.07  4920.6 1187.85
  4978.0 1182.51  4985.1 1182.44  4992.2 1180.72  5003.1 1180.16  5003.3 1179.66
  5007.1 1180.16  5010.9 1182.26  5025.2 1184.41  5119.1 1192.14  5125.6 1193.57
  5155.8 1196.84  5195.9 1204.83  5216.0 1206.77  5246.2 1213.25  5276.3 1217.52
#Mann=5,-1,0
  4610.4    0.05       0  4715.9    0.12       0  4920.6    0.05       0
  5003.1    0.03       0  5007.1    0.05       0
Bank Sta=5003.1,5007.1
Exp/Cntr=0.3,0.1

Type RM Length L Ch R = 1,25707,473,473,473
BEGIN DESCRIPTION:
LITTLE LLANO 052 51.0
END DESCRIPTION:
XS GIS Cut Line= 3
      2829155.66     10268053.09      2829064.75     10267967.00
      2828955.67     10268003.12
#Sta/Elev= 30
  4874.8 1179.43  4878.2 1179.43  4881.8 1178.66  4896.0 1178.05  4902.9 1177.22
  4910.2 1177.16  4917.0 1177.31  4924.3 1175.80  4931.2 1174.85  4938.5 1174.25
  4973.7 1170.37  4980.9 1170.26  4987.8 1168.76  4995.1 1168.52  4997.2 1167.10
  4997.4 1166.60  5000.9 1166.60  5001.2 1167.10  5003.9 1168.52  5009.5 1168.25
  5030.4 1168.19  5051.7 1171.00  5062.1 1172.14  5067.3 1171.11  5083.3 1173.10
  5093.8 1174.61  5099.0 1173.28  5104.4 1176.56  5112.3 1178.57  5114.9 1178.57
#Mann=3,-1,0
  4874.8    0.05       0  4997.2    0.05       0  5001.2    0.05       0
Bank Sta=4997.2,5001.2
Exp/Cntr=0.3,0.1

Type RM Length L Ch R = 1,25234,496,496,496
BEGIN DESCRIPTION:
LITTLE LLANO 052 50.0
END DESCRIPTION:
XS GIS Cut Line= 3
      2829205.71     10267603.12      2829062.00     10267563.00
      2828805.70     10267853.10
#Sta/Elev= 30
  4850.8 1170.10  4902.1 1166.02  4907.3 1166.51  4915.7 1165.20  4941.4 1160.93
  4946.6 1161.31  4975.4 1158.61  4980.8 1157.22  5002.4 1156.78  5002.7 1156.28
  5006.4 1156.78  5012.0 1158.30  5018.6 1157.72  5026.2 1159.06  5032.9 1157.81
  5047.1 1160.15  5053.7 1159.38  5061.3 1160.23  5068.0 1159.63  5075.5 1160.59
  5082.2 1160.05  5089.7 1160.98  5121.8 1161.44  5132.4 1161.93  5153.3 1160.64
  5174.2 1160.97  5196.0 1162.19  5202.7 1163.80  5259.5 1166.50  5387.1 1174.48
#Mann=5,-1,0
  4850.8    0.05       0  4915.7    0.12       0  5002.4    0.07       0
  5006.4    0.12       0  5121.8    0.05       0
Bank Sta=5002.4,5006.4
Exp/Cntr=0.3,0.1

Type RM Length L Ch R = 1,24738,490,490,490
BEGIN DESCRIPTION:
LITTLE LLANO 052 49.0
END DESCRIPTION:
XS GIS Cut Line= 3
      2829005.65     10267203.11      2828902.25     10267188.00
      2828605.70     10267153.11
#Sta/Elev= 30
  4895.5 1152.72  4915.7 1150.70  4925.4 1149.97  4930.4 1150.00  4935.9 1149.03
  4966.2 1147.78  4976.3 1146.54  4986.4 1142.79  4995.4 1141.68  4997.6 1141.04
  4997.9 1140.54  5001.4 1140.54  5001.6 1141.04  5016.7 1144.19  5067.0 1148.65
  5083.4 1149.92  5088.4 1149.80  5137.5 1153.91  5157.6 1156.11  5171.5 1156.82
  5177.8 1157.67  5187.9 1158.23  5238.2 1163.62  5248.3 1165.22  5254.6 1167.42
  5259.6 1166.73  5278.5 1171.38  5288.5 1174.24  5296.1 1178.03  5298.6 1178.03
#Mann=3,-1,0
  4895.5    0.05       0  4997.6    0.05       0  5001.6    0.05       0
Bank Sta=4997.6,5001.6
Exp/Cntr=0.3,0.1

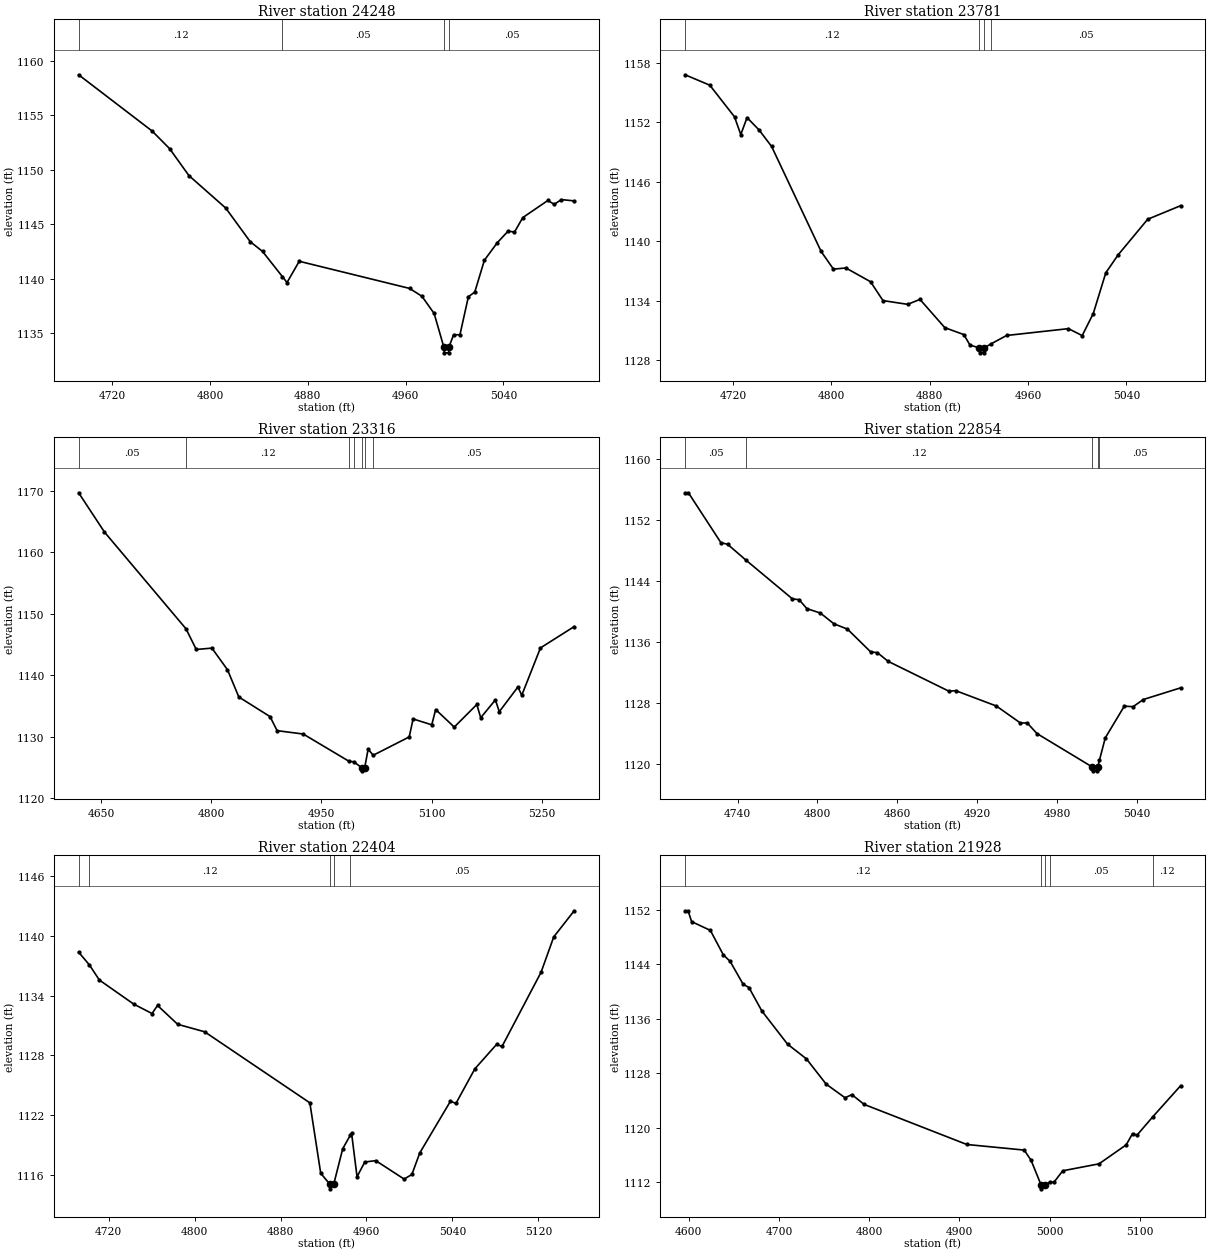
Type RM Length L Ch R = 1,24248,467,467,467
BEGIN DESCRIPTION:
LITTLE LLANO 052 48.0
END DESCRIPTION:
XS GIS Cut Line= 3
      2829255.69     10266703.11      2828949.00     10266724.00
      2828855.64     10266753.13
#Sta/Elev= 30
  4692.6 1158.72  4752.7 1153.56  4767.0 1151.94  4782.8 1149.47  4812.9 1146.49
  4832.9 1143.41  4843.0 1142.51  4859.3 1140.19  4863.0 1139.66  4873.0 1141.61
  4963.2 1139.12  4973.3 1138.40  4983.3 1136.82  4991.3 1133.71  4991.6 1133.21
  4995.1 1133.21  4995.3 1133.71  4999.2 1134.87  5004.4 1134.87  5011.3 1138.36
  5016.5 1138.78  5024.4 1141.71  5034.9 1143.31  5043.8 1144.38  5049.0 1144.29
  5055.8 1145.62  5076.3 1147.19  5081.5 1146.83  5087.3 1147.27  5097.8 1147.15
#Mann=4,-1,0
  4692.6    0.12       0  4859.3    0.05       0  4991.3    0.05       0
  4995.3    0.05       0
Bank Sta=4991.3,4995.3
Exp/Cntr=0.3,0.1

Type RM Length L Ch R = 1,23781,465,465,465
BEGIN DESCRIPTION:
LITTLE LLANO 052 47.0
END DESCRIPTION:
XS GIS Cut Line= 3
      2829255.66     10266403.11      2828938.50     10266368.00
      2828855.73     10266353.12
#Sta/Elev= 30
  4680.9 1156.79  4701.0 1155.74  4721.1 1152.55  4726.2 1150.76  4731.3 1152.47
  4741.2 1151.21  4751.3 1149.56  4791.6 1138.97  4801.6 1137.19  4811.7 1137.31
  4831.8 1135.92  4841.9 1134.02  4862.0 1133.64  4872.0 1134.14  4892.2 1131.29
  4907.7 1130.59  4912.7 1129.53  4920.3 1129.25  4920.6 1128.75  4924.1 1128.75
  4924.3 1129.25  4930.2 1129.68  4942.5 1130.50  4992.8 1131.19  5004.0 1130.49
  5013.0 1132.71  5023.2 1136.82  5033.3 1138.64  5057.3 1142.22  5084.1 1143.59
#Mann=4,-1,0
  4680.9    0.12       0  4920.3    0.05       0  4924.3    0.12       0
  4930.2    0.05       0
Bank Sta=4920.3,4924.3
Exp/Cntr=0.3,0.1

Type RM Length L Ch R = 1,23316,462,462,462
BEGIN DESCRIPTION:
LITTLE LLANO 052 46.0
END DESCRIPTION:
XS GIS Cut Line= 3
      2829355.65     10266253.09      2829032.25     10266053.00
      2828755.71     10266153.10
#Sta/Elev= 30
  4619.7 1169.63  4654.9 1163.24  4765.8 1147.53  4779.8 1144.17  4801.1 1144.39
  4822.3 1140.87  4837.7 1136.45  4880.2 1133.26  4889.8 1130.98  4925.4 1130.43
  4988.1 1125.97  4994.1 1125.93  5005.0 1124.95  5005.2 1124.45  5009.0 1124.95
  5013.7 1127.97  5020.6 1126.98  5069.6 1129.96  5074.9 1132.88  5100.3 1131.93
  5105.6 1134.41  5130.9 1131.56  5161.6 1135.23  5166.9 1133.08  5186.9 1135.98
  5192.2 1134.06  5217.5 1138.07  5222.8 1136.73  5248.2 1144.42  5294.1 1147.89
#Mann=7,-1,0
  4619.7    0.05       0  4765.8    0.12       0  4988.1    0.05       0
  4994.1    0.12       0  5005.0    0.07       0  5009.0    0.12       0
  5020.6    0.05       0
Bank Sta=5005,5009
Exp/Cntr=0.3,0.1

Type RM Length L Ch R = 1,22854,450,450,450
BEGIN DESCRIPTION:
LITTLE LLANO 052 45.0
END DESCRIPTION:
XS GIS Cut Line= 3
      2829355.69     10265653.11      2829061.00     10265706.00
      2829005.65     10265753.14
#Sta/Elev= 30
  4700.6 1155.54  4703.1 1155.54  4727.5 1149.00  4732.5 1148.79  4746.1 1146.74
  4781.2 1141.63  4786.2 1141.53  4792.0 1140.36  4802.2 1139.77  4812.4 1138.36
  4822.5 1137.67  4839.9 1134.69  4845.0 1134.58  4853.0 1133.45  4898.7 1129.53
  4903.8 1129.60  4934.3 1127.59  4952.4 1125.36  4957.5 1125.37  4964.8 1123.98
  5006.4 1119.59  5006.7 1119.09  5010.2 1119.09  5010.4 1119.59  5011.7 1120.46
  5016.1 1123.41  5030.4 1127.57  5037.0 1127.50  5044.7 1128.44  5072.7 1129.97
#Mann=5,-1,0
  4700.6    0.05       0  4746.1    0.12       0  5006.4    0.07       0
  5010.4    0.12       0  5011.7    0.05       0
Bank Sta=5006.4,5010.4
Exp/Cntr=0.3,0.1

Type RM Length L Ch R = 1,22404,476,476,476
BEGIN DESCRIPTION:
LITTLE LLANO 052 44.0
END DESCRIPTION:
XS GIS Cut Line= 3
      2829305.67     10265303.12      2829005.00     10265369.00
      2828855.65     10265403.12
#Sta/Elev= 30
  4692.2 1138.37  4702.2 1137.09  4711.5 1135.57  4743.4 1133.16  4760.5 1132.21
  4765.6 1133.02  4784.3 1131.13  4809.4 1130.38  4907.3 1123.25  4917.4 1116.19
  4925.6 1115.12  4925.9 1114.62  4929.6 1115.12  4937.9 1118.65  4945.0 1120.01
  4946.1 1120.22  4951.2 1115.83  4958.4 1117.31  4968.6 1117.45  4995.0 1115.60
  5002.2 1116.06  5009.6 1118.23  5038.1 1123.41  5043.2 1123.19  5060.8 1126.66
  5081.0 1129.11  5086.1 1128.91  5122.4 1136.35  5134.2 1139.90  5153.2 1142.52
#Mann=5,-1,0
  4692.2    0.05       0  4702.2    0.12       0  4925.6    0.05       0
  4929.6    0.12       0  4945.0    0.05       0
Bank Sta=4925.6,4929.6
Exp/Cntr=0.3,0.1

Type RM Length L Ch R = 1,21928,469,469,469
BEGIN DESCRIPTION:
LITTLE LLANO 052 43.0
END DESCRIPTION:
XS GIS Cut Line= 3
      2829405.70     10265203.13      2829100.00     10264939.00
      2828955.69     10264953.11
#Sta/Elev= 30
  4596.0 1151.82  4599.3 1151.82  4603.2 1150.23  4624.0 1148.94  4638.3 1145.36
  4645.9 1144.39  4660.2 1141.06  4666.8 1140.54  4681.0 1137.12  4709.5 1132.24
  4730.4 1130.08  4752.3 1126.37  4773.2 1124.37  4780.8 1124.83  4794.3 1123.40
  4908.1 1117.51  4971.7 1116.69  4979.3 1115.19  4990.6 1111.50  4990.8 1111.00
  4994.6 1111.50  4999.8 1111.98  5004.7 1111.98  5014.4 1113.65  5054.6 1114.67
  5084.7 1117.46  5091.7 1119.11  5096.7 1118.89  5114.3 1121.60  5145.0 1126.14
#Mann=5,-1,0
  4596.0    0.12       0  4990.6    0.03       0  4994.6    0.12       0
  4999.8    0.05       0  5114.3    0.12       0
Bank Sta=4990.6,4994.6
Exp/Cntr=0.3,0.1

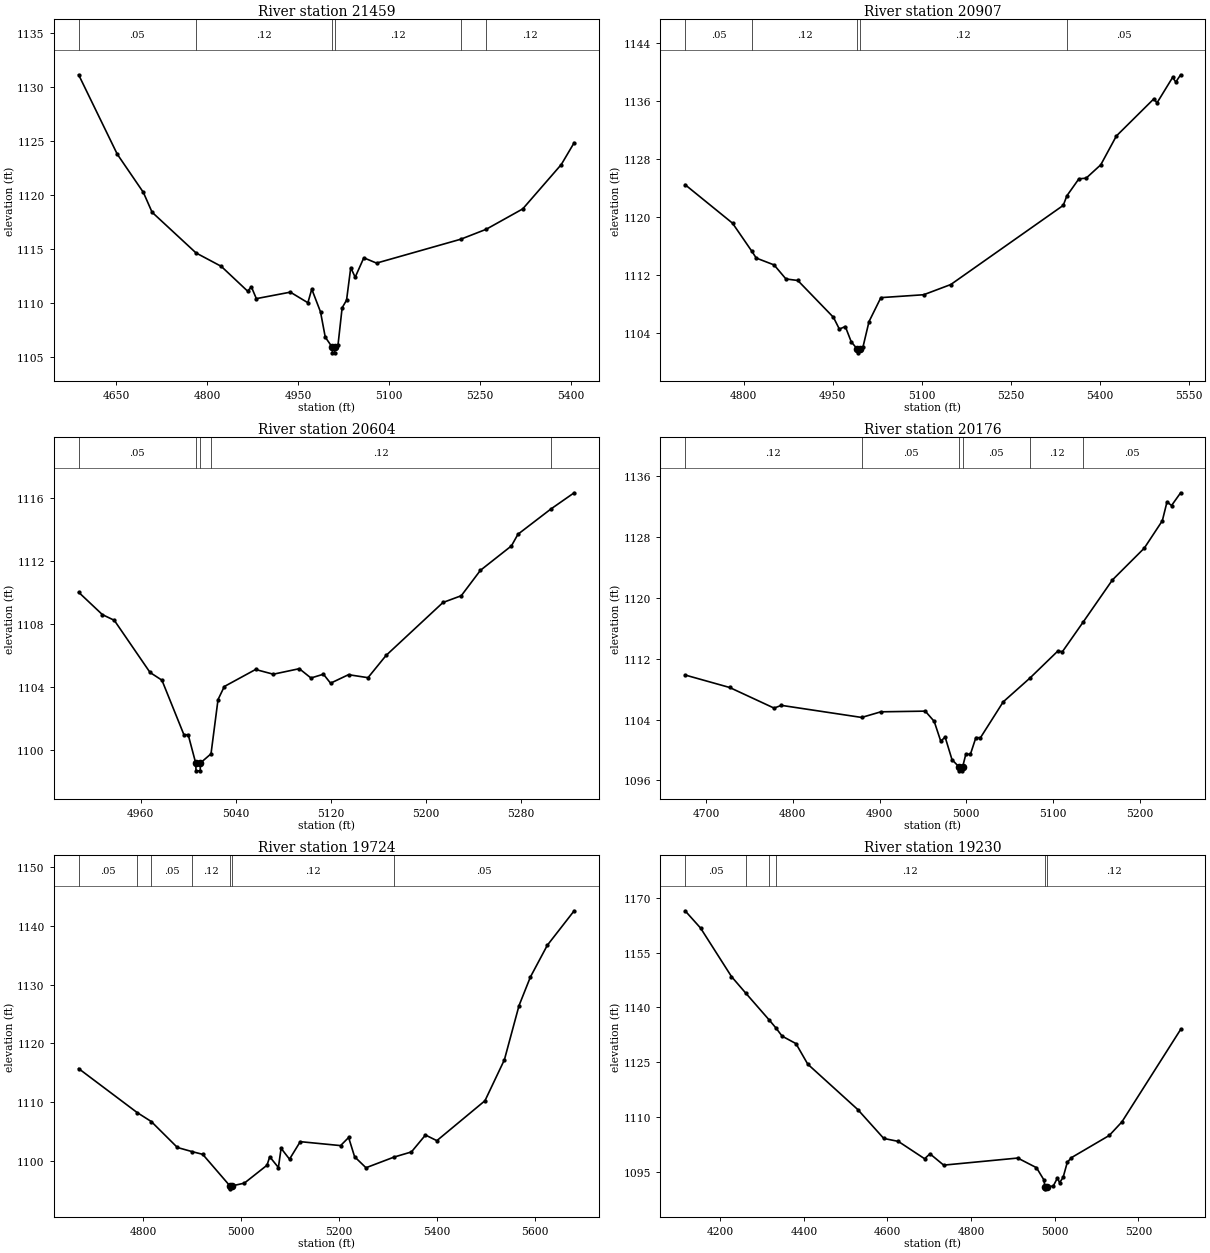
Type RM Length L Ch R = 1,21459,552,552,552
BEGIN DESCRIPTION:
LITTLE LLANO 052 42.0
END DESCRIPTION:
XS GIS Cut Line= 3
      2829505.67     10265003.10      2829251.00     10264680.00
      2828955.70     10264403.12
#Sta/Elev= 30
  4588.6 1131.09  4652.2 1123.74  4695.2 1120.20  4709.6 1118.36  4782.0 1114.59
  4823.5 1113.35  4866.8 1111.06  4873.2 1111.44  4881.3 1110.36  4937.3 1110.96
  4966.2 1109.98  4972.6 1111.24  4987.0 1109.13  4994.8 1106.80  5006.5 1105.84
  5006.7 1105.34  5010.2 1105.34  5010.5 1105.84  5015.8 1106.06  5022.6 1109.51
  5029.9 1110.22  5036.8 1113.23  5044.1 1112.34  5058.3 1114.14  5079.3 1113.65
  5217.9 1115.86  5259.8 1116.78  5320.1 1118.67  5383.6 1122.78  5404.8 1124.80
#Mann=6,-1,0
  4588.6    0.05       0  4782.0    0.12       0  5006.5    0.07       0
  5010.5    0.12       0  5217.9    0.05       0  5259.8    0.12       0
Bank Sta=5006.5,5010.5
Exp/Cntr=0.3,0.1

Type RM Length L Ch R = 1,20907,303,303,303
BEGIN DESCRIPTION:
Mapping XS c731b34f
END DESCRIPTION:
XS GIS Cut Line= 3
      2829722.76     10264993.05      2829707.74     10264632.55
      2829557.53     10264181.93
#Sta/Elev= 30
  4700.9 1124.48  4780.9 1119.16  4813.6 1115.26  4820.9 1114.34  4851.0 1113.39
  4871.0 1111.45  4891.0 1111.24  4951.1 1106.15  4961.1 1104.52  4971.1 1104.88
  4981.1 1102.77  4991.5 1101.74  4991.8 1101.24  4995.5 1101.74  5001.1 1102.11
  5011.1 1105.56  5031.1 1108.87  5103.3 1109.27  5149.0 1110.68  5338.7 1121.62
  5344.8 1122.94  5365.1 1125.29  5377.3 1125.38  5402.0 1127.23  5428.3 1131.21
  5491.6 1136.35  5496.8 1135.78  5523.2 1139.31  5528.5 1138.66  5536.7 1139.67
#Mann=5,-1,0
  4700.9    0.05       0  4813.6    0.12       0  4991.5    0.07       0
  4995.5    0.12       0  5344.8    0.05       0
Bank Sta=4991.5,4995.5
Exp/Cntr=0.3,0.1

Type RM Length L Ch R = 1,20604,428,428,428
BEGIN DESCRIPTION:
LITTLE LLANO 052 40.0
END DESCRIPTION:
XS GIS Cut Line= 3
      2830005.68     10264803.14      2830009.00     10264711.00
      2829905.67     10264403.07
#Sta/Elev= 30
  4907.8 1110.03  4927.8 1108.61  4937.8 1108.25  4967.9 1104.94  4977.9 1104.45
  4996.4 1100.99  5000.0 1100.99  5006.3 1099.20  5006.6 1098.70  5010.1 1098.70
  5010.3 1099.20  5019.2 1099.78  5025.1 1103.22  5030.4 1104.05  5056.7 1105.13
  5071.6 1104.83  5093.5 1105.18  5103.3 1104.59  5113.8 1104.83  5119.8 1104.26
  5134.9 1104.80  5151.3 1104.61  5166.5 1106.02  5214.4 1109.38  5229.8 1109.81
  5245.9 1111.42  5272.0 1112.97  5277.5 1113.71  5305.2 1115.31  5324.8 1116.34
#Mann=5,-1,0
  4907.8    0.05       0  5006.3    0.05       0  5010.3    0.05       0
  5019.2    0.12       0  5305.2    0.05       0
Bank Sta=5006.3,5010.3
Exp/Cntr=0.3,0.1

Type RM Length L Ch R = 1,20176,452,452,452
BEGIN DESCRIPTION:
LITTLE LLANO 052 39.0
END DESCRIPTION:
XS GIS Cut Line= 3
      2830255.69     10264803.14      2830184.75     10264487.00
      2830105.68     10264253.10
#Sta/Elev= 30
  4676.0 1109.85  4727.3 1108.21  4778.5 1105.50  4786.9 1105.86  4879.4 1104.27
  4901.5 1105.01  4952.7 1105.10  4963.0 1103.75  4970.5 1101.16  4975.6 1101.68
  4983.5 1098.72  4991.7 1097.75  4992.0 1097.25  4995.5 1097.25  4995.7 1097.75
  4999.4 1099.43  5004.7 1099.43  5011.0 1101.62  5016.3 1101.61  5042.5 1106.32
  5073.2 1109.44  5105.4 1113.00  5110.7 1112.92  5134.6 1116.81  5168.3 1122.35
  5205.0 1126.53  5225.8 1130.13  5231.2 1132.62  5236.4 1132.13  5246.9 1133.81
#Mann=6,-1,0
  4676.0    0.12       0  4879.4    0.05       0  4991.7    0.05       0
  4995.7    0.05       0  5073.2    0.12       0  5134.6    0.05       0
Bank Sta=4991.7,4995.7
Exp/Cntr=0.3,0.1

Type RM Length L Ch R = 1,19724,494,494,494
BEGIN DESCRIPTION:
LITTLE LLANO 052 38.0
END DESCRIPTION:
XS GIS Cut Line= 3
      2830655.66     10264853.07      2830477.75     10264573.00
      2830755.67     10263953.15
#Sta/Elev= 30
  4668.2 1115.70  4787.5 1108.22  4816.4 1106.69  4869.7 1102.27  4899.9 1101.56
  4921.4 1101.10  4976.9 1095.73  4977.2 1095.23  4981.1 1095.73  5006.3 1096.20
  5052.6 1099.25  5058.1 1100.69  5075.8 1098.86  5081.3 1102.13  5098.5 1100.28
  5120.4 1103.26  5202.7 1102.59  5219.1 1103.97  5231.3 1100.69  5254.5 1098.82
  5311.9 1100.64  5347.2 1101.51  5375.9 1104.39  5399.1 1103.43  5497.3 1110.23
  5536.9 1117.19  5566.8 1126.43  5590.0 1131.29  5624.5 1136.69  5679.3 1142.56
#Mann=7,-1,0
  4668.2    0.05       0  4787.5    0.12       0  4816.4    0.05       0
  4899.9    0.12       0  4976.9    0.07       0  4981.1    0.12       0
  5311.9    0.05       0
Bank Sta=4976.9,4981.1
Exp/Cntr=0.3,0.1

Type RM Length L Ch R = 1,19230,357,357,357
BEGIN DESCRIPTION:
LITTLE LLANO 052 37.0
END DESCRIPTION:
XS GIS Cut Line= 3
      2831255.68     10265153.09      2830880.00     10264353.00
      2830905.69     10264053.10
#Sta/Elev= 30
  4116.1 1166.43  4153.1 1161.70  4227.0 1148.42  4261.4 1143.85  4317.9 1136.44
  4332.8 1134.41  4348.1 1132.11  4381.2 1130.06  4409.5 1124.42  4529.1 1112.00
  4591.1 1104.10  4625.9 1103.29  4688.8 1098.54  4701.6 1099.89  4734.4 1096.79
  4911.5 1098.73  4956.3 1096.09  4973.6 1092.83  4976.9 1090.80  4977.2 1090.30
  4981.2 1090.80  4996.4 1091.07  5006.5 1093.28  5011.5 1091.97  5020.0 1093.43
  5030.0 1097.58  5040.0 1098.85  5130.4 1104.92  5160.5 1108.62  5301.0 1133.94
#Mann=6,-1,0
  4116.1    0.05       0  4261.4    0.12       0  4317.9    0.05       0
  4332.8    0.12       0  4976.9    0.07       0  4981.2    0.12       0
Bank Sta=4976.9,4981.2
Exp/Cntr=0.3,0.1

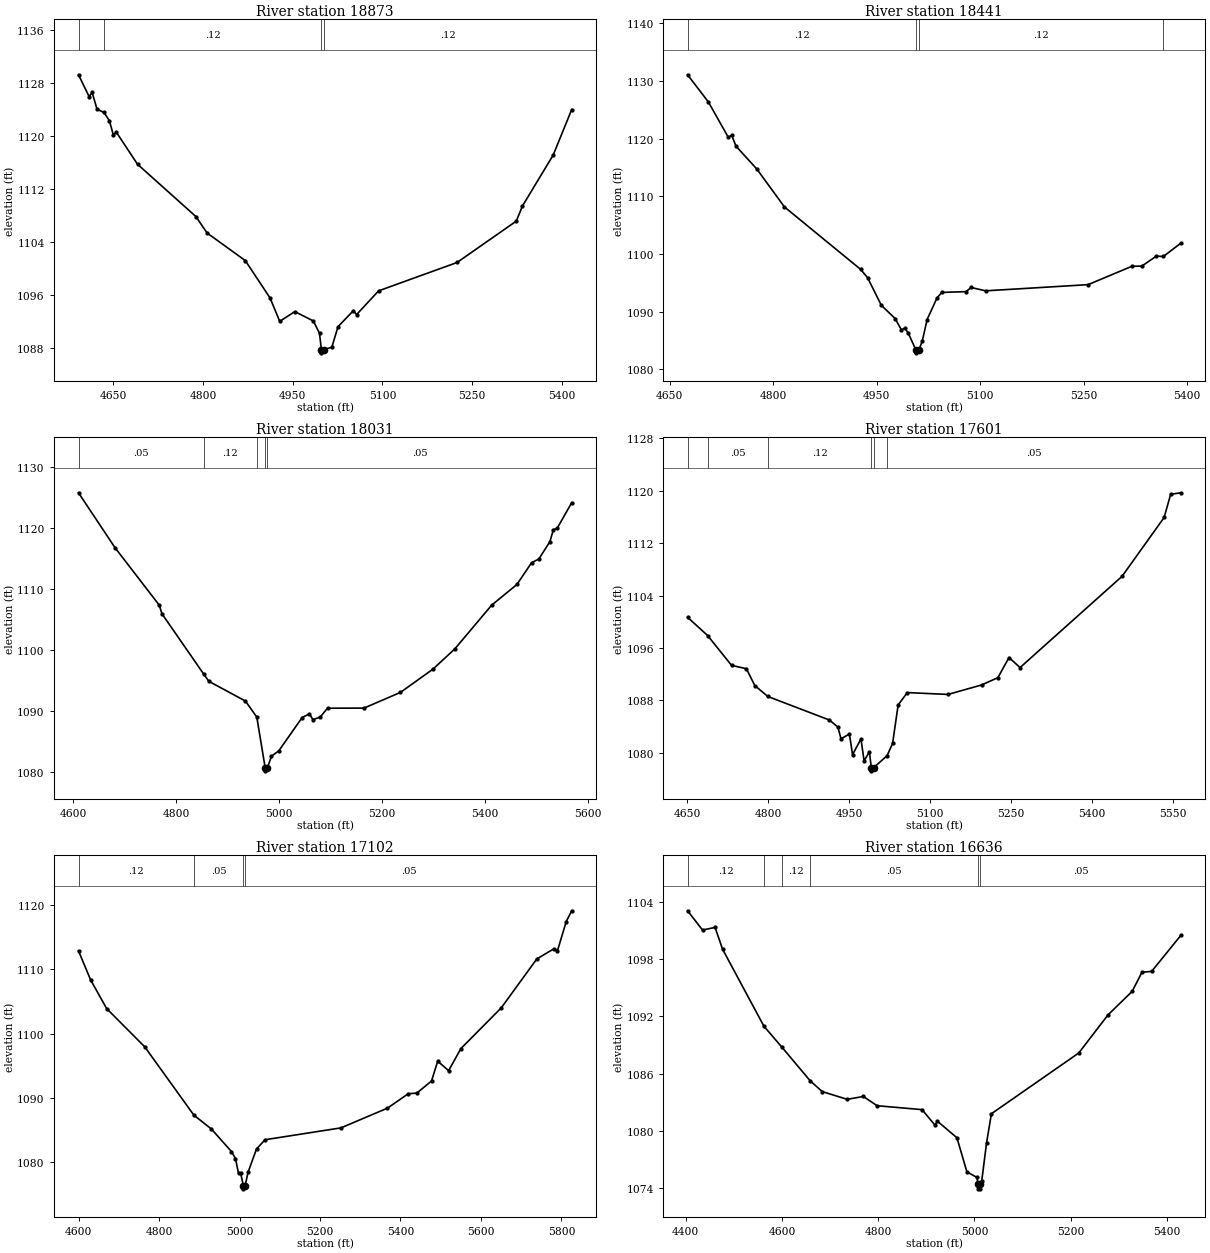
Type RM Length L Ch R = 1,18873,432,432,432
BEGIN DESCRIPTION:
LITTLE LLANO 052 36.0
END DESCRIPTION:
XS GIS Cut Line= 3
      2831205.68     10264903.11      2831102.75     10264508.00
      2831005.68     10264103.07
#Sta/Elev= 30
  4591.7 1129.25  4609.4 1125.96  4614.5 1126.58  4622.7 1124.05  4634.4 1123.56
  4643.4 1122.31  4649.9 1120.17  4655.0 1120.58  4690.4 1115.75  4788.0 1107.86
  4806.7 1105.38  4870.7 1101.21  4912.0 1095.58  4928.2 1092.05  4953.4 1093.52
  4984.4 1092.11  4994.7 1090.25  4997.8 1087.80  4998.0 1087.30  5002.1 1087.80
  5015.3 1088.14  5025.6 1091.24  5051.5 1093.68  5056.7 1093.07  5093.5 1096.65
  5224.7 1100.93  5323.8 1107.17  5334.1 1109.46  5385.5 1117.14  5416.4 1124.00
#Mann=4,-1,0
  4591.7    0.05       0  4634.4    0.12       0  4997.8    0.07       0
  5002.1    0.12       0
Bank Sta=4997.8,5002.1
Exp/Cntr=0.3,0.1

Type RM Length L Ch R = 1,18441,410,410,410
BEGIN DESCRIPTION:
LITTLE LLANO 052 35.0
END DESCRIPTION:
XS GIS Cut Line= 3
      2831455.69     10264853.07      2831481.50     10264530.00
      2831205.70     10264253.13
#Sta/Elev= 30
  4675.9 1131.06  4706.0 1126.35  4734.8 1120.25  4739.9 1120.55  4746.1 1118.68
  4776.2 1114.73  4816.3 1108.15  4926.7 1097.33  4936.7 1095.91  4956.8 1091.09
  4976.8 1088.80  4985.8 1086.85  4990.8 1087.14  4995.9 1086.26  5006.8 1083.36
  5007.1 1082.86  5011.2 1083.36  5016.1 1084.89  5023.1 1088.63  5037.3 1092.34
  5044.3 1093.33  5079.7 1093.47  5086.8 1094.19  5108.0 1093.61  5256.5 1094.68
  5320.1 1097.87  5334.3 1097.89  5355.5 1099.63  5365.6 1099.56  5390.8 1101.86
#Mann=4,-1,0
  4675.9    0.12       0  5006.8    0.07       0  5011.2    0.12       0
  5365.6    0.05       0
Bank Sta=5006.8,5011.2
Exp/Cntr=0.3,0.1

Type RM Length L Ch R = 1,18031,430,430,430
BEGIN DESCRIPTION:
LITTLE LLANO 052 34.0
END DESCRIPTION:
XS GIS Cut Line= 3
      2831905.68     10264753.10      2831843.50     10264369.00
      2831455.65     10263953.08
#Sta/Elev= 30
  4610.9 1125.72  4681.8 1116.73  4767.6 1107.34  4773.0 1105.91  4854.5 1095.99
  4864.1 1094.86  4935.1 1091.63  4957.2 1089.00  4973.4 1080.71  4973.7 1080.21
  4977.8 1080.71  4985.7 1082.61  5000.0 1083.50  5045.2 1088.93  5059.3 1089.54
  5066.2 1088.58  5080.3 1089.01  5094.5 1090.46  5165.4 1090.48  5236.2 1093.05
  5299.7 1096.88  5342.2 1100.21  5413.1 1107.31  5462.4 1110.72  5490.7 1114.26
  5504.9 1114.88  5526.4 1117.72  5533.2 1119.68  5540.6 1119.92  5568.7 1124.09
#Mann=5,-1,0
  4610.9    0.05       0  4854.5    0.12       0  4957.2    0.05       0
  4973.4    0.05       0  4977.8    0.05       0
Bank Sta=4973.4,4977.8
Exp/Cntr=0.3,0.1

Type RM Length L Ch R = 1,17601,499,499,499
BEGIN DESCRIPTION:
LITTLE LLANO 052 33.0
END DESCRIPTION:
XS GIS Cut Line= 3
      2832055.69     10264553.10      2832234.25     10264253.00
      2832105.69     10263703.13
#Sta/Elev= 30
  4650.8 1100.69  4687.9 1097.91  4732.2 1093.36  4759.8 1092.84  4775.4 1090.27
  4799.4 1088.61  4913.7 1085.01  4929.3 1083.94  4935.1 1082.15  4950.7 1082.88
  4956.5 1079.73  4972.1 1082.13  4977.9 1078.77  4987.7 1080.18  4991.2 1077.76
  4991.6 1077.26  4995.8 1077.76  5020.4 1079.56  5030.7 1081.45  5041.0 1087.32
  5058.0 1089.20  5133.4 1088.92  5195.8 1090.37  5225.8 1091.48  5246.4 1094.55
  5266.9 1093.02  5455.9 1106.94  5533.9 1115.92  5546.0 1119.46  5564.7 1119.69
#Mann=6,-1,0
  4650.8    0.12       0  4687.9    0.05       0  4799.4    0.12       0
  4991.2    0.07       0  4995.8    0.12       0  5020.4    0.05       0
Bank Sta=4991.2,4995.8
Exp/Cntr=0.3,0.1

Type RM Length L Ch R = 1,17102,466,466,466
BEGIN DESCRIPTION:
LITTLE LLANO 052 32.0
END DESCRIPTION:
XS GIS Cut Line= 3
      2832605.68     10264803.11      2832593.50     10264403.00
      2832155.71     10263703.15
#Sta/Elev= 30
  4599.7 1112.83  4629.7 1108.33  4669.7 1103.87  4764.4 1097.93  4886.4 1087.34
  4929.9 1085.19  4979.9 1081.69  4989.9 1080.59  4997.4 1078.30  5002.7 1078.30
  5009.4 1076.40  5009.7 1075.90  5014.0 1076.40  5020.9 1078.44  5042.1 1082.08
  5063.3 1083.52  5252.0 1085.36  5367.5 1088.42  5419.4 1090.66  5440.6 1090.76
  5477.1 1092.63  5492.5 1095.71  5519.6 1094.24  5550.2 1097.67  5650.5 1103.99
  5738.9 1111.58  5781.3 1113.15  5790.2 1112.86  5812.0 1117.38  5825.5 1119.05
#Mann=4,-1,0
  4599.7    0.12       0  4886.4    0.05       0  5009.4    0.03       0
  5014.0    0.05       0
Bank Sta=5009.4,5014
Exp/Cntr=0.3,0.1

Type RM Length L Ch R = 1,16636,402,402,402
BEGIN DESCRIPTION:
LITTLE LLANO 052 31.0
END DESCRIPTION:
XS GIS Cut Line= 3
      2832805.68     10264703.13      2832962.00     10264128.00
      2832905.68     10263703.12
#Sta/Elev= 30
  4404.0 1103.07  4435.1 1101.05  4461.1 1101.33  4476.6 1099.05  4562.5 1090.98
  4600.4 1088.75  4658.9 1085.24  4683.8 1084.12  4735.6 1083.31  4769.1 1083.61
  4797.8 1082.64  4891.1 1082.23  4917.9 1080.61  4923.0 1081.02  4963.6 1079.28
  4984.3 1075.71  5005.0 1075.13  5007.6 1074.43  5008.0 1073.93  5012.0 1073.93
  5012.3 1074.43  5015.0 1074.70  5025.1 1078.74  5035.2 1081.80  5216.8 1088.17
  5277.3 1092.15  5327.7 1094.63  5347.9 1096.62  5368.1 1096.72  5428.6 1100.48
#Mann=6,-1,0
  4404.0    0.12       0  4562.5    0.05       0  4600.4    0.12       0
  4658.9    0.05       0  5007.6    0.05       0  5012.3    0.05       0
Bank Sta=5007.6,5012.3
Exp/Cntr=0.3,0.1

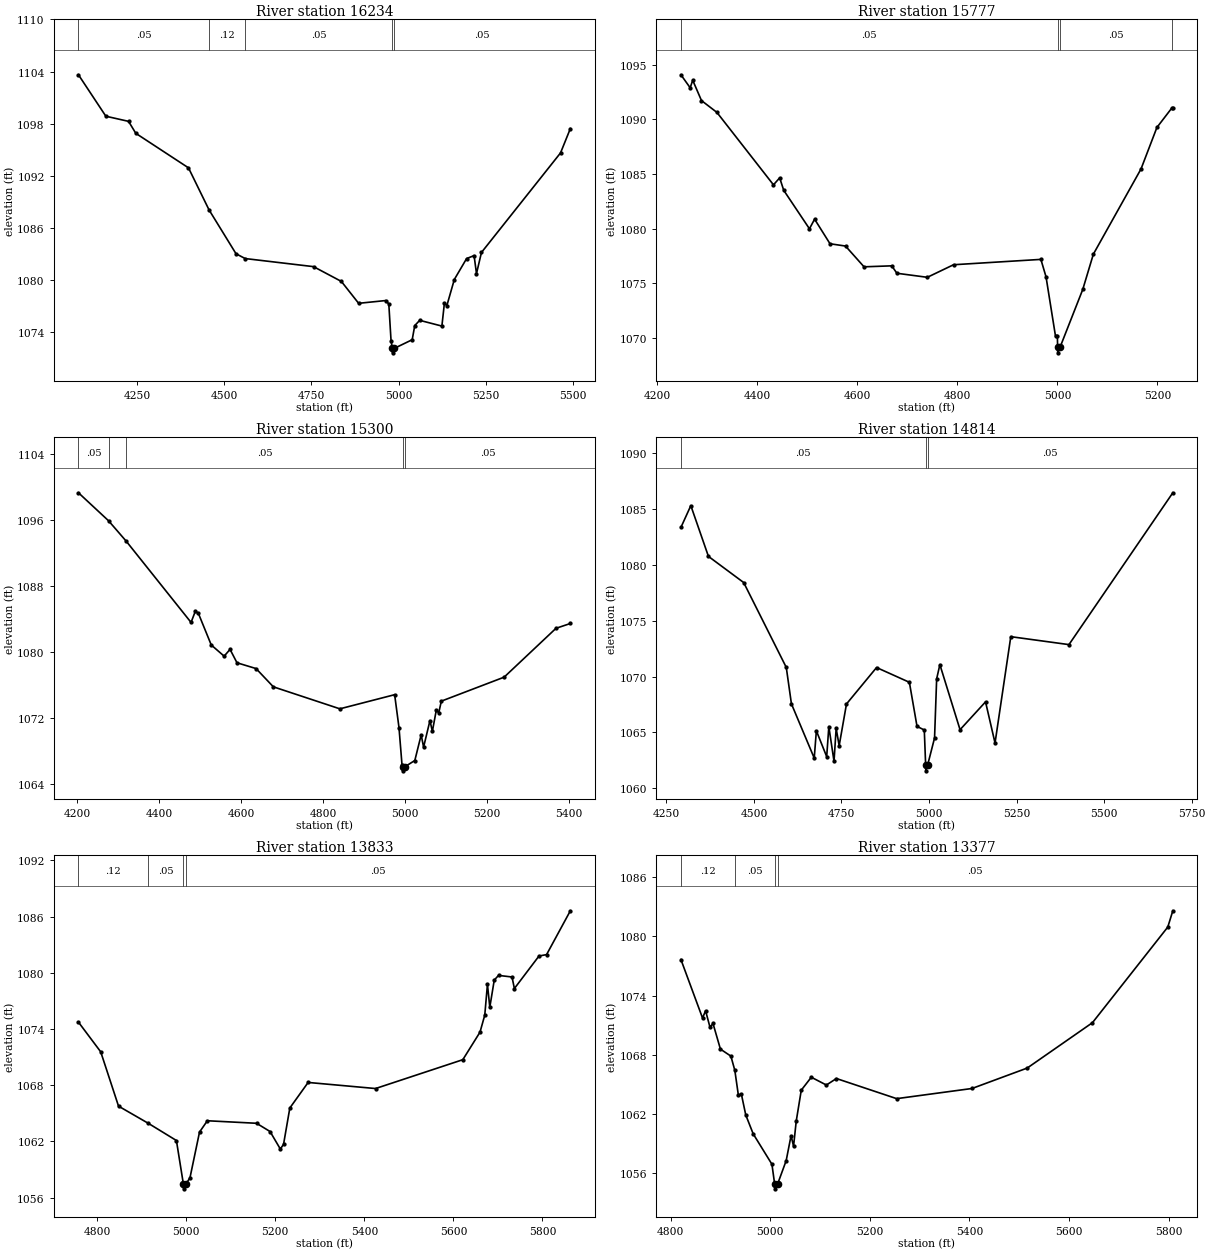
Type RM Length L Ch R = 1,16234,457,457,457
BEGIN DESCRIPTION:
LITTLE LLANO 052 30.0
END DESCRIPTION:
XS GIS Cut Line= 3
      2832805.69     10264853.10      2833343.50     10264110.00
      2833005.69     10263753.12
#Sta/Elev= 30
  4082.7 1103.63  4161.2 1098.86  4226.2 1098.27  4247.0 1096.89  4397.8 1092.92
  4456.7 1088.08  4534.0 1083.03  4560.2 1082.48  4755.9 1081.55  4835.6 1079.85
  4885.1 1077.33  4963.2 1077.65  4971.5 1077.25  4977.9 1073.03  4981.7 1072.13
  4982.1 1071.63  4986.4 1072.13  5038.5 1073.14  5045.8 1074.77  5060.0 1075.37
  5123.5 1074.71  5130.8 1077.38  5137.7 1077.06  5159.1 1080.07  5194.3 1082.48
  5215.7 1082.82  5222.6 1080.75  5236.8 1083.18  5463.3 1094.64  5491.4 1097.44
#Mann=5,-1,0
  4082.7    0.05       0  4456.7    0.12       0  4560.2    0.05       0
  4981.7    0.03       0  4986.4    0.05       0
Bank Sta=4981.7,4986.4
Exp/Cntr=0.3,0.1

Type RM Length L Ch R = 1,15777,477,477,477
BEGIN DESCRIPTION:
LITTLE LLANO 052 29.0
END DESCRIPTION:
XS GIS Cut Line= 3
      2833905.67     10264653.07      2833731.50     10263921.00
      2833655.68     10263703.11
#Sta/Elev= 30
  4247.5 1094.08  4266.0 1092.89  4271.1 1093.58  4288.6 1091.72  4319.4 1090.64
  4432.5 1084.01  4444.9 1084.65  4453.0 1083.51  4504.4 1079.99  4514.7 1080.87
  4545.5 1078.62  4576.5 1078.41  4613.5 1076.51  4668.9 1076.60  4679.2 1075.92
  4740.0 1075.55  4792.4 1076.70  4967.0 1077.19  4977.3 1075.59  4996.3 1070.14
  5000.0 1070.14  5000.4 1069.14  5000.7 1068.64  5005.2 1069.14  5050.7 1074.44
  5071.9 1077.67  5167.2 1085.47  5198.9 1089.26  5228.9 1091.05  5230.7 1091.05
#Mann=4,-1,0
  4247.5    0.05       0  5000.4    0.05       0  5005.2    0.05       0
  5228.9    0.12       0
Bank Sta=5000.4,5005.2
Exp/Cntr=0.3,0.1

Type RM Length L Ch R = 1,15300,486,486,486
BEGIN DESCRIPTION:
LITTLE LLANO 052 28.0
END DESCRIPTION:
XS GIS Cut Line= 3
      2833905.70     10264753.07      2834162.50     10263999.00
      2833955.69     10263653.11
#Sta/Elev= 30
  4203.4 1099.25  4276.7 1095.87  4319.8 1093.40  4478.0 1083.57  4488.6 1084.94
  4496.0 1084.65  4527.3 1080.84  4558.7 1079.49  4573.1 1080.31  4590.0 1078.69
  4636.5 1077.99  4678.7 1075.78  4840.9 1073.12  4974.5 1074.83  4985.1 1070.85
  4992.4 1066.37  4994.8 1066.12  4995.1 1065.62  4999.6 1066.12  5023.7 1066.87
  5039.2 1069.97  5045.1 1068.49  5060.6 1071.70  5066.5 1070.40  5076.2 1072.99
  5082.0 1072.63  5088.4 1074.05  5241.5 1076.95  5368.0 1082.86  5403.0 1083.44
#Mann=5,-1,0
  4203.4    0.05       0  4276.7    0.12       0  4319.8    0.05       0
  4994.8    0.03       0  4999.6    0.05       0
Bank Sta=4994.8,4999.6
Exp/Cntr=0.3,0.1

Type RM Length L Ch R = 1,14814,981,981,981
BEGIN DESCRIPTION:
LITTLE LLANO 052 27.0
END DESCRIPTION:
XS GIS Cut Line= 3
      2834055.66     10264503.13      2834631.25     10264090.00
      2835005.71     10263503.08
#Sta/Elev= 30
  4291.5 1083.34  4319.8 1085.29  4370.1 1080.75  4470.8 1078.41  4592.4 1070.82
  4607.1 1067.56  4672.2 1062.71  4678.3 1065.15  4707.8 1062.84  4713.9 1065.53
  4728.7 1062.42  4734.8 1065.37  4743.4 1063.82  4764.3 1067.55  4850.2 1070.81
  4943.9 1069.49  4965.7 1065.55  4986.5 1065.22  4990.4 1062.07  4990.8 1061.57
  4995.9 1062.07  5015.8 1064.51  5021.8 1069.80  5031.0 1071.07  5088.6 1065.25
  5161.4 1067.74  5188.5 1064.06  5233.5 1073.57  5399.6 1072.86  5696.2 1086.44
#Mann=3,-1,0
  4291.5    0.05       0  4990.4    0.03       0  4995.9    0.05       0
Bank Sta=4990.4,4995.9
Exp/Cntr=0.3,0.1

Type RM Length L Ch R = 1,13833,456,456,456
BEGIN DESCRIPTION:
LITTLE LLANO 052 26.0
END DESCRIPTION:
XS GIS Cut Line= 3
      2834905.68     10264603.09      2834903.50     10264361.00
      2835205.70     10263553.07
#Sta/Elev= 30
  4757.9 1074.74  4807.9 1071.57  4847.9 1065.77  4915.0 1063.93  4977.9 1062.10
  4993.6 1057.44  4994.1 1056.94  4999.2 1057.44  5008.4 1058.13  5029.8 1063.00
  5047.4 1064.21  5157.9 1063.94  5188.2 1063.06  5211.3 1061.19  5218.5 1061.69
  5232.6 1065.57  5273.7 1068.30  5425.1 1067.65  5621.1 1070.73  5659.7 1073.67
  5670.4 1075.49  5676.4 1078.77  5681.7 1076.33  5691.7 1079.23  5701.3 1079.73
  5731.6 1079.56  5736.9 1078.33  5792.2 1081.80  5809.2 1081.95  5862.6 1086.63
#Mann=4,-1,0
  4757.9    0.12       0  4915.0    0.05       0  4993.6    0.03       0
  4999.2    0.05       0
Bank Sta=4993.6,4999.2
Exp/Cntr=0.3,0.1

Type RM Length L Ch R = 1,13377,538,538,538
BEGIN DESCRIPTION:
LITTLE LLANO 052 25.0
END DESCRIPTION:
XS GIS Cut Line= 3
      2835255.67     10264553.14      2835356.50     10264405.00
      2835255.68     10263603.11
#Sta/Elev= 30
  4820.8 1077.65  4864.2 1071.72  4870.3 1072.46  4879.2 1070.78  4885.2 1071.17
  4900.1 1068.57  4921.1 1067.86  4929.0 1066.42  4936.1 1063.91  4942.1 1064.02
  4951.0 1061.89  4965.9 1059.98  5003.5 1056.90  5008.9 1054.91  5009.4 1054.41
  5015.0 1054.91  5032.1 1057.27  5041.9 1059.80  5046.9 1058.73  5052.3 1061.28
  5062.4 1064.41  5082.5 1065.72  5112.8 1064.93  5132.9 1065.59  5253.9 1063.55
  5405.1 1064.58  5515.9 1066.65  5646.9 1071.25  5798.1 1080.94  5808.2 1082.59
#Mann=4,-1,0
  4820.8    0.12       0  4929.0    0.05       0  5008.9    0.05       0
  5015.0    0.05       0
Bank Sta=5008.9,5015
Exp/Cntr=0.3,0.1