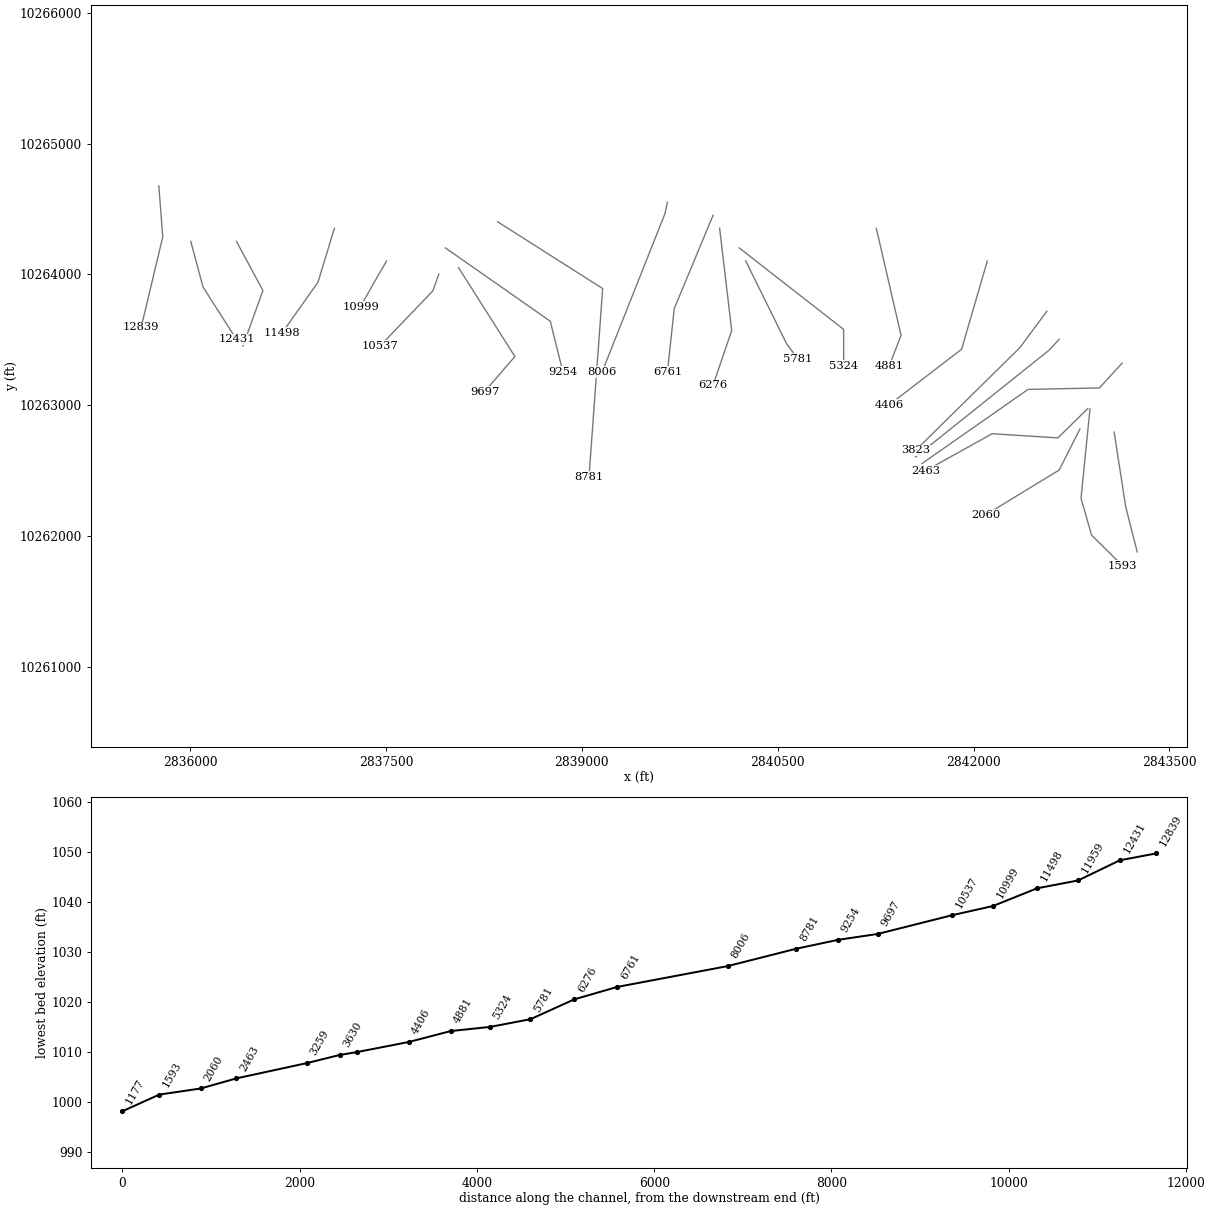
HEC-RAS study LITTLE LLANO 052.prj: LITTLE LLANO 052 Base Level Engineering

--- LITTLE LLANO 052.g01 (geometry) --- (continued)

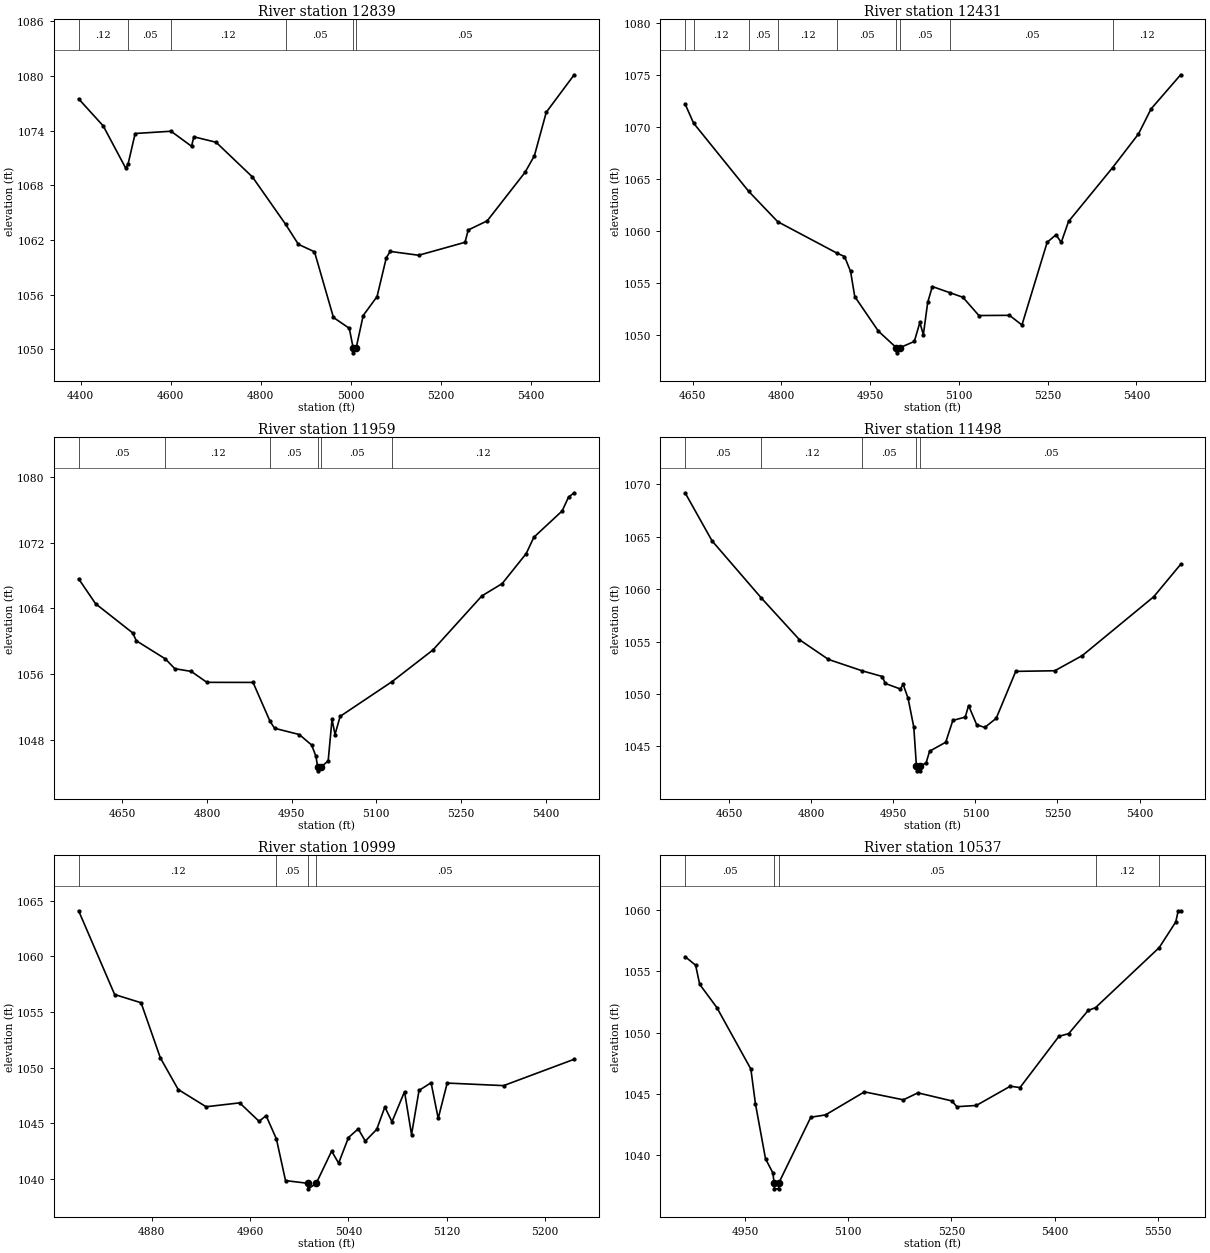
Type RM Length L Ch R = 1,12839,408,408,408
BEGIN DESCRIPTION:
Mapping XS 1ec953e6
END DESCRIPTION:
XS GIS Cut Line= 3
      2835761.38     10264677.62      2835791.43     10264287.06
      2835626.45     10263597.13
#Sta/Elev= 30
  4395.8 1077.47  4450.5 1074.50  4500.6 1069.85  4505.9 1070.37  4521.4 1073.67
  4601.1 1073.92  4646.7 1072.27  4651.8 1073.31  4701.2 1072.71  4782.1 1068.90
  4855.5 1063.73  4884.1 1061.52  4919.9 1060.70  4962.0 1053.50  4997.2 1052.31
  5006.0 1050.12  5006.5 1049.62  5012.3 1050.12  5028.1 1053.71  5058.9 1055.79
  5079.5 1060.06  5088.2 1060.74  5151.4 1060.32  5254.3 1061.74  5261.5 1063.09
  5303.6 1064.09  5387.7 1069.41  5408.5 1071.23  5434.9 1076.00  5496.9 1080.11
#Mann=6,-1,0
  4395.8    0.12       0  4505.9    0.05       0  4601.1    0.12       0
  4855.5    0.05       0  5006.0    0.05       0  5012.3    0.05       0
Bank Sta=5006,5012.3
Exp/Cntr=0.3,0.1

Type RM Length L Ch R = 1,12431,472,472,472
BEGIN DESCRIPTION:
LITTLE LLANO 052 23.0
END DESCRIPTION:
XS GIS Cut Line= 3
      2836005.68     10264253.12      2836100.00     10263903.00
      2836355.66     10263503.15
#Sta/Elev= 30
  4637.4 1072.21  4651.8 1070.36  4744.7 1063.81  4793.9 1060.88  4894.5 1057.84
  4906.7 1057.53  4917.0 1056.09  4924.0 1053.68  4963.9 1050.35  4994.2 1048.76
  4994.7 1048.26  5000.6 1048.76  5024.7 1049.36  5034.0 1051.18  5039.9 1050.01
  5047.3 1053.12  5055.1 1054.64  5085.6 1054.03  5106.7 1053.61  5133.8 1051.85
  5185.4 1051.87  5206.5 1050.94  5249.1 1058.90  5264.0 1059.62  5272.9 1058.89
  5285.2 1060.90  5359.7 1066.09  5403.4 1069.33  5424.7 1071.74  5474.6 1075.02
#Mann=9,-1,0
  4637.4    0.05       0  4651.8    0.12       0  4744.7    0.05       0
  4793.9    0.12       0  4894.5    0.05       0  4994.2    0.07       0
  5000.6    0.05       0  5085.6    0.05       0  5359.7    0.12       0
Bank Sta=4994.2,5000.6
Exp/Cntr=0.3,0.1

Type RM Length L Ch R = 1,11959,461,461,461
BEGIN DESCRIPTION:
LITTLE LLANO 052 22.0
END DESCRIPTION:
XS GIS Cut Line= 3
      2836355.69     10264253.10      2836558.50     10263877.00
      2836405.68     10263453.11
#Sta/Elev= 30
  4572.7 1067.59  4602.7 1064.56  4668.4 1061.01  4674.9 1060.05  4726.4 1057.84
  4743.1 1056.65  4772.2 1056.32  4799.9 1054.99  4881.7 1054.98  4911.7 1050.26
  4919.8 1049.40  4963.6 1048.64  4985.5 1047.36  4993.1 1045.99  4996.1 1044.72
  4996.6 1044.22  5002.6 1044.72  5014.8 1045.43  5021.6 1050.49  5026.9 1048.64
  5036.0 1050.85  5128.0 1055.08  5200.4 1058.93  5287.1 1065.51  5323.1 1067.01
  5365.6 1070.66  5379.2 1072.65  5429.3 1075.85  5440.6 1077.53  5450.6 1078.06
#Mann=6,-1,0
  4572.7    0.05       0  4726.4    0.12       0  4911.7    0.05       0
  4996.1    0.05       0  5002.6    0.05       0  5128.0    0.12       0
Bank Sta=4996.1,5002.6
Exp/Cntr=0.3,0.1

Type RM Length L Ch R = 1,11498,499,499,499
BEGIN DESCRIPTION:
LITTLE LLANO 052 21.0
END DESCRIPTION:
XS GIS Cut Line= 3
      2837105.69     10264353.13      2836980.25     10263941.00
      2836705.70     10263553.14
#Sta/Elev= 30
  4569.2 1069.19  4618.5 1064.60  4708.1 1059.18  4778.3 1055.17  4831.3 1053.29
  4893.1 1052.20  4929.8 1051.66  4935.1 1051.00  4962.7 1050.47  4967.9 1050.91
  4976.9 1049.57  4987.3 1046.84  4992.1 1043.16  4992.6 1042.66  4998.4 1042.66
  4998.9 1043.16  5009.7 1043.39  5016.2 1044.53  5045.7 1045.39  5058.7 1047.47
  5081.4 1047.79  5087.5 1048.89  5102.3 1047.06  5117.1 1046.80  5138.0 1047.67
  5173.7 1052.15  5245.1 1052.21  5295.5 1053.66  5426.0 1059.27  5475.2 1062.36
#Mann=5,-1,0
  4569.2    0.05       0  4708.1    0.12       0  4893.1    0.05       0
  4992.1    0.05       0  4998.9    0.05       0
Bank Sta=4992.1,4998.9
Exp/Cntr=0.3,0.1

Type RM Length L Ch R = 1,10999,462,462,462
BEGIN DESCRIPTION:
LITTLE LLANO 052 20.0
END DESCRIPTION:
XS GIS Cut Line= 3
      2837505.66     10264103.07      2837415.25     10263948.00
      2837305.67     10263753.09
#Sta/Elev= 30
  4820.5 1064.11  4849.8 1056.58  4871.3 1055.84  4887.0 1050.88  4901.5 1048.04
  4924.2 1046.49  4951.5 1046.84  4967.3 1045.18  4973.0 1045.69  4981.4 1043.59
  4988.8 1039.85  5006.8 1039.61  5007.3 1039.11  5013.8 1039.61  5026.3 1042.50
  5032.0 1041.42  5040.0 1043.72  5047.9 1044.50  5053.7 1043.40  5063.0 1044.46
  5069.6 1046.47  5075.4 1045.14  5085.6 1047.84  5091.3 1043.99  5097.4 1047.96
  5107.2 1048.65  5113.0 1045.44  5120.3 1048.62  5166.2 1048.39  5223.6 1050.76
#Mann=4,-1,0
  4820.5    0.12       0  4981.4    0.05       0  5006.8    0.03       0
  5013.8    0.05       0
Bank Sta=5006.8,5013.8
Exp/Cntr=0.3,0.1

Type RM Length L Ch R = 1,10537,840,840,840
BEGIN DESCRIPTION:
LITTLE LLANO 052 19.0
END DESCRIPTION:
XS GIS Cut Line= 3
      2837905.68     10264003.10      2837859.25     10263874.00
      2837455.69     10263453.12
#Sta/Elev= 30
  4862.8 1056.21  4878.1 1055.51  4884.0 1053.95  4908.9 1052.06  4958.4 1047.04
  4965.0 1044.22  4979.7 1039.72  4990.3 1038.58  4992.2 1037.77  4992.7 1037.27
  4998.7 1037.27  4999.2 1037.77  5045.5 1043.11  5066.9 1043.30  5123.5 1045.18
  5180.1 1044.53  5201.2 1045.10  5250.6 1044.44  5257.8 1043.97  5286.1 1044.07
  5335.5 1045.64  5349.6 1045.53  5406.2 1049.71  5420.4 1049.93  5448.7 1051.82
  5459.4 1052.05  5552.0 1056.95  5576.0 1059.04  5579.6 1059.95  5583.1 1059.95
#Mann=5,-1,0
  4862.8    0.05       0  4992.2    0.03       0  4999.2    0.05       0
  5459.4    0.12       0  5552.0    0.05       0
Bank Sta=4992.2,4999.2
Exp/Cntr=0.3,0.1

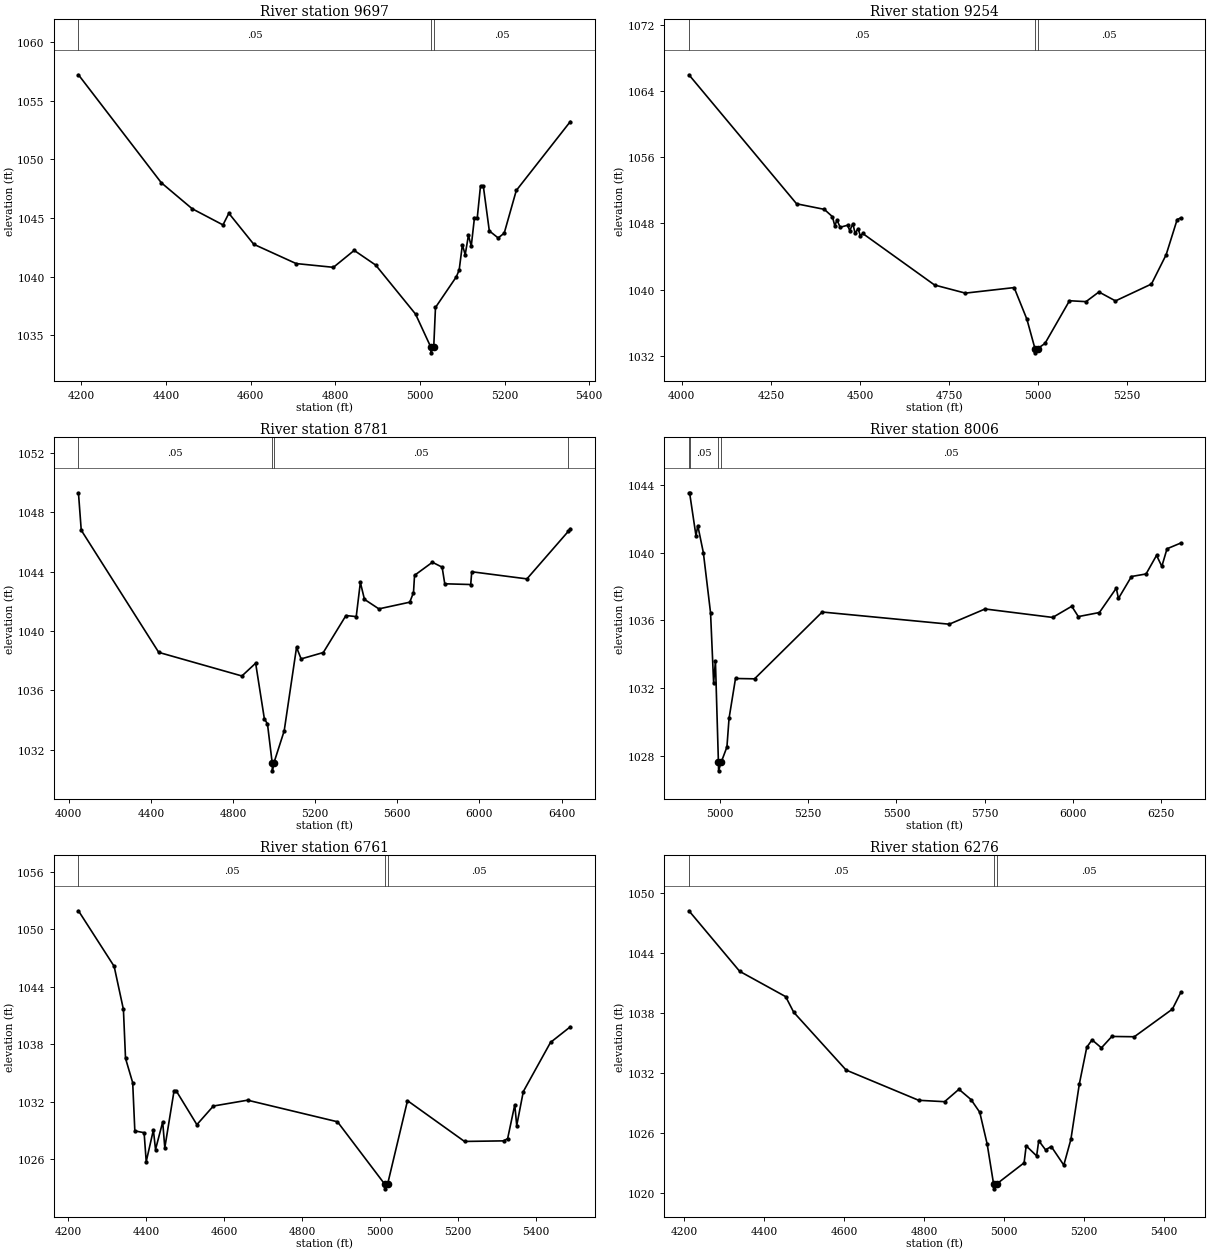
Type RM Length L Ch R = 1,9697,443,443,443
BEGIN DESCRIPTION:
LITTLE LLANO 052 18.0
END DESCRIPTION:
XS GIS Cut Line= 3
      2838055.70     10264053.09      2838488.00     10263372.00
      2838255.72     10263103.15
#Sta/Elev= 30
  4193.3 1057.19  4389.0 1048.00  4461.8 1045.79  4534.7 1044.41  4548.6 1045.40
  4607.5 1042.76  4707.5 1041.12  4795.6 1040.80  4844.7 1042.24  4895.5 1040.99
  4989.6 1036.82  5025.5 1034.02  5026.0 1033.52  5032.6 1034.02  5036.7 1037.38
  5086.1 1040.00  5092.7 1040.58  5100.3 1042.72  5106.9 1041.87  5114.6 1043.53
  5121.2 1042.60  5128.8 1045.03  5135.4 1045.01  5143.1 1047.74  5149.7 1047.72
  5163.9 1043.90  5184.8 1043.30  5199.1 1043.71  5227.6 1047.34  5355.3 1053.21
#Mann=3,-1,0
  4193.3    0.05       0  5025.5    0.03       0  5032.6    0.05       0
Bank Sta=5025.5,5032.6
Exp/Cntr=0.3,0.1

Type RM Length L Ch R = 1,9254,473,473,473
BEGIN DESCRIPTION:
LITTLE LLANO 052 17.0
END DESCRIPTION:
XS GIS Cut Line= 3
      2837955.67     10264203.12      2838759.00     10263642.00
      2838855.68     10263253.14
#Sta/Elev= 30
  4020.1 1065.98  4322.3 1050.38  4400.0 1049.71  4422.7 1048.83  4429.6 1047.72
  4435.7 1048.42  4444.5 1047.54  4465.4 1047.79  4471.5 1047.13  4480.2 1047.97
  4486.3 1046.84  4495.1 1047.37  4501.1 1046.51  4508.0 1046.79  4709.6 1040.56
  4796.0 1039.58  4932.9 1040.25  4968.7 1036.42  4991.4 1032.86  4991.9 1032.36
  4998.5 1032.86  5019.5 1033.50  5088.2 1038.66  5134.6 1038.55  5170.8 1039.72
  5217.3 1038.64  5318.3 1040.68  5359.5 1044.22  5390.4 1048.47  5400.7 1048.68
#Mann=3,-1,0
  4020.1    0.05       0  4991.4    0.03       0  4998.5    0.05       0
Bank Sta=4991.4,4998.5
Exp/Cntr=0.3,0.1

Type RM Length L Ch R = 1,8781,775,775,775
BEGIN DESCRIPTION:
LITTLE LLANO 052 16.0
END DESCRIPTION:
XS GIS Cut Line= 3
      2838355.66     10264403.13      2839160.00     10263892.00
      2839055.68     10262453.08
#Sta/Elev= 30
  4047.0 1049.31  4060.6 1046.79  4438.0 1038.56  4843.1 1036.97  4910.0 1037.83
  4952.4 1034.09  4967.6 1033.74  4990.9 1031.08  4991.4 1030.58  4998.1 1031.08
  5049.0 1033.27  5109.2 1038.90  5131.5 1038.12  5239.5 1038.55  5349.8 1041.04
  5399.9 1040.97  5420.0 1043.27  5440.0 1042.13  5510.2 1041.49  5660.6 1041.94
  5678.8 1042.59  5683.9 1043.75  5770.9 1044.63  5818.2 1044.30  5831.1 1043.18
  5957.5 1043.13  5962.5 1043.99  6231.2 1043.51  6433.2 1046.72  6442.7 1046.89
#Mann=4,-1,0
  4047.0    0.05       0  4990.9    0.03       0  4998.1    0.05       0
  6433.2    0.12       0
Bank Sta=4990.9,4998.1
Exp/Cntr=0.3,0.1

Type RM Length L Ch R = 1,8006,1245,1245,1245
BEGIN DESCRIPTION:
LITTLE LLANO 052 15.0
END DESCRIPTION:
XS GIS Cut Line= 3
      2839655.69     10264553.15      2839637.75     10264467.00
      2839155.69     10263253.12
#Sta/Elev= 30
  4912.0 1043.54  4913.9 1043.54  4932.0 1041.00  4937.1 1041.60  4952.9 1040.00
  4973.3 1036.44  4982.0 1032.30  4987.1 1033.58  4995.6 1027.60  4996.1 1027.10
  5003.3 1027.60  5019.7 1028.51  5025.7 1030.20  5044.0 1032.56  5098.0 1032.54
  5289.7 1036.49  5649.8 1035.77  5751.3 1036.67  5943.0 1036.17  5997.0 1036.83
  6015.6 1036.22  6075.3 1036.46  6123.2 1037.90  6129.3 1037.29  6166.2 1038.59
  6207.6 1038.74  6237.3 1039.84  6252.3 1039.19  6267.0 1040.23  6306.1 1040.57
#Mann=4,-1,0
  4912.0    0.12       0  4913.9    0.05       0  4995.6    0.03       0
  5003.3    0.05       0
Bank Sta=4995.6,5003.3
Exp/Cntr=0.3,0.1

Type RM Length L Ch R = 1,6761,485,485,485
BEGIN DESCRIPTION:
LITTLE LLANO 052 14.0
END DESCRIPTION:
XS GIS Cut Line= 3
      2840005.69     10264453.13      2839708.25     10263739.00
      2839655.69     10263253.14
#Sta/Elev= 30
  4226.4 1051.92  4318.0 1046.13  4341.8 1041.64  4347.2 1036.54  4365.6 1034.00
  4371.1 1028.98  4394.9 1028.79  4400.3 1025.78  4418.7 1029.07  4424.2 1027.04
  4442.6 1029.91  4448.0 1027.22  4471.8 1033.17  4477.2 1033.16  4530.3 1029.63
  4572.6 1031.57  4660.4 1032.18  4891.1 1029.93  5012.1 1023.44  5012.6 1022.94
  5019.8 1023.44  5070.8 1032.13  5217.1 1027.88  5317.7 1027.94  5327.8 1028.18
  5346.1 1031.70  5351.1 1029.54  5368.0 1033.08  5437.8 1038.20  5488.7 1039.83
#Mann=3,-1,0
  4226.4    0.05       0  5012.1    0.05       0  5019.8    0.05       0
Bank Sta=5012.1,5019.8
Exp/Cntr=0.3,0.1

Type RM Length L Ch R = 1,6276,495,495,495
BEGIN DESCRIPTION:
LITTLE LLANO 052 13.0
END DESCRIPTION:
XS GIS Cut Line= 3
      2840055.68     10264353.14      2840148.25     10263571.00
      2840005.70     10263153.15
#Sta/Elev= 30
  4212.4 1048.25  4339.2 1042.20  4454.1 1039.67  4474.2 1038.11  4605.2 1032.33
  4786.4 1029.31  4851.2 1029.17  4887.1 1030.41  4917.3 1029.38  4939.1 1028.11
  4957.6 1024.94  4973.6 1020.96  4974.1 1020.46  4981.8 1020.96  5049.9 1023.06
  5055.1 1024.76  5081.2 1023.75  5086.5 1025.27  5103.4 1024.36  5117.8 1024.69
  5149.1 1022.83  5166.8 1025.40  5188.0 1030.96  5206.5 1034.61  5219.7 1035.35
  5243.1 1034.55  5269.2 1035.69  5325.3 1035.66  5420.4 1038.42  5441.5 1040.09
#Mann=3,-1,0
  4212.4    0.05       0  4973.6    0.05       0  4981.8    0.05       0
Bank Sta=4973.6,4981.8
Exp/Cntr=0.3,0.1

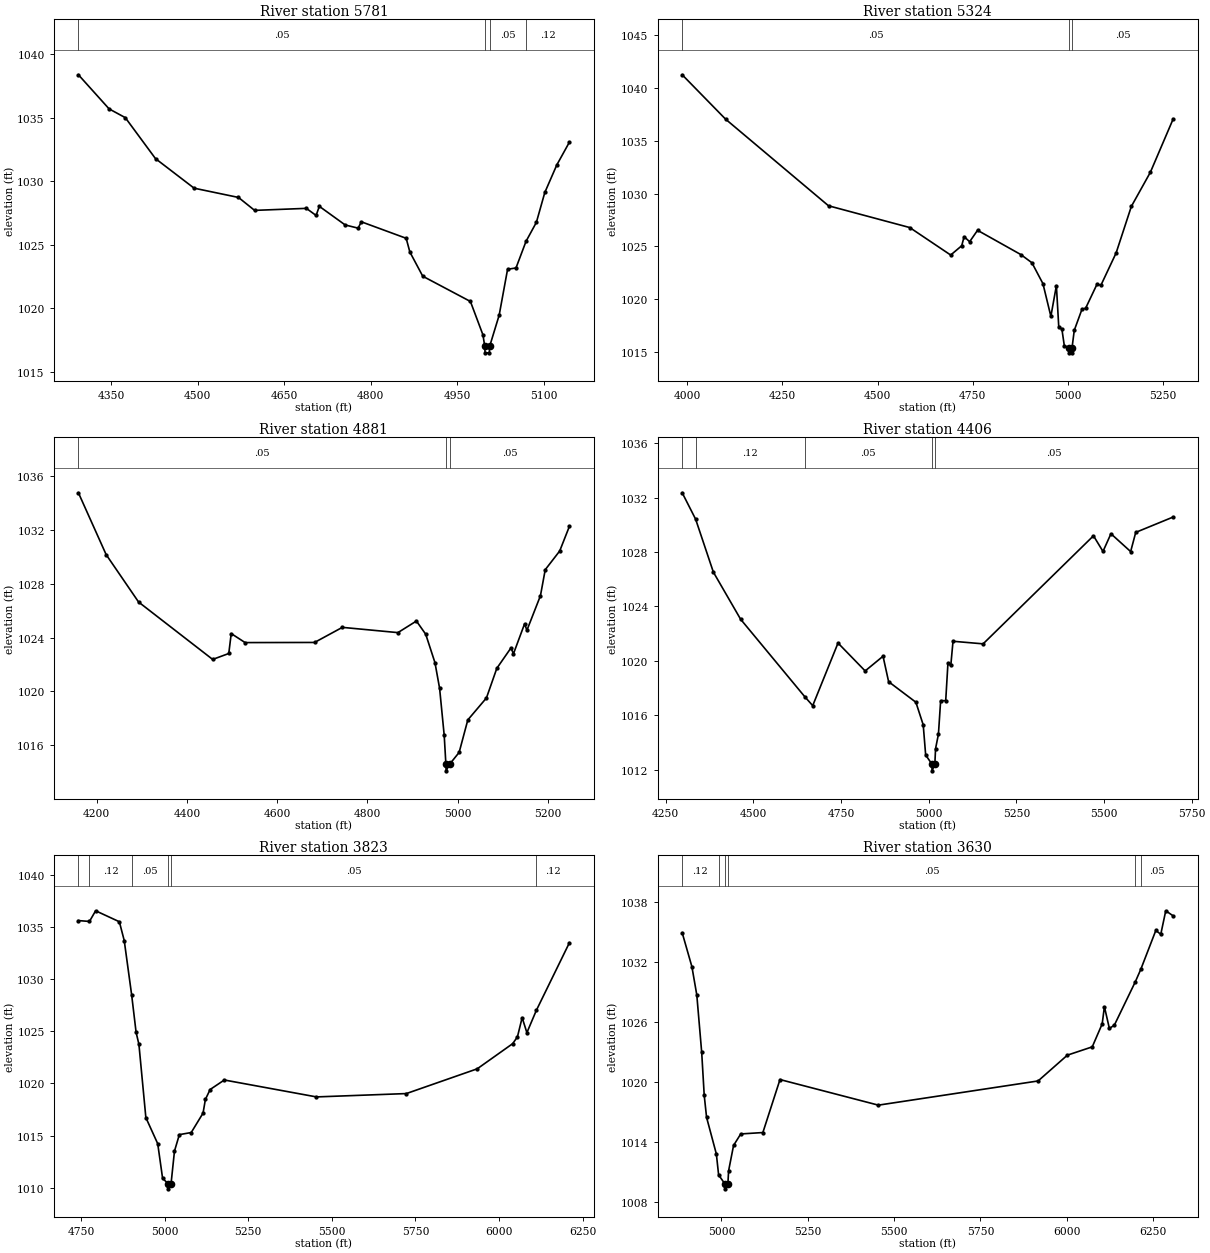
Type RM Length L Ch R = 1,5781,457,457,457
BEGIN DESCRIPTION:
LITTLE LLANO 052 12.0
END DESCRIPTION:
XS GIS Cut Line= 3
      2840255.68     10264103.13      2840568.75     10263469.00
      2840655.70     10263353.09
#Sta/Elev= 30
  4292.8 1038.40  4346.1 1035.71  4374.2 1035.02  4426.6 1031.79  4493.6 1029.46
  4570.6 1028.73  4598.6 1027.71  4688.4 1027.87  4705.3 1027.31  4710.9 1028.03
  4755.8 1026.56  4778.2 1026.31  4783.8 1026.81  4861.6 1025.51  4868.0 1024.43
  4890.4 1022.52  4973.1 1020.53  4994.9 1017.89  4998.0 1016.98  4998.5 1016.48
  5005.9 1016.48  5006.4 1016.98  5023.0 1019.45  5037.6 1023.07  5052.2 1023.17
  5069.6 1025.27  5087.6 1026.77  5102.2 1029.12  5123.0 1031.29  5144.9 1033.09
#Mann=4,-1,0
  4292.8    0.05       0  4998.0    0.03       0  5006.4    0.05       0
  5069.6    0.12       0
Bank Sta=4998,5006.4
Exp/Cntr=0.3,0.1

Type RM Length L Ch R = 1,5324,443,443,443
BEGIN DESCRIPTION:
LITTLE LLANO 052 11.0
END DESCRIPTION:
XS GIS Cut Line= 3
      2840205.68     10264203.11      2841005.00     10263580.00
      2841005.68     10263303.10
#Sta/Elev= 30
  3986.5 1041.24  4100.6 1037.04  4371.0 1028.85  4584.5 1026.79  4692.1 1024.19
  4721.1 1025.07  4727.4 1025.93  4741.9 1025.45  4762.7 1026.53  4876.7 1024.23
  4905.6 1023.46  4934.6 1021.48  4955.4 1018.39  4969.9 1021.30  4976.2 1017.35
  4984.3 1017.20  4990.7 1015.62  5002.6 1015.44  5003.1 1014.94  5010.6 1014.94
  5011.1 1015.44  5016.9 1017.07  5036.9 1019.04  5046.9 1019.17  5076.9 1021.45
  5086.9 1021.33  5126.9 1024.39  5166.9 1028.79  5216.9 1032.02  5276.9 1037.07
#Mann=3,-1,0
  3986.5    0.05       0  5002.6    0.03       0  5011.1    0.05       0
Bank Sta=5002.6,5011.1
Exp/Cntr=0.3,0.1

Type RM Length L Ch R = 1,4881,475,475,475
BEGIN DESCRIPTION:
LITTLE LLANO 052 10.0
END DESCRIPTION:
XS GIS Cut Line= 3
      2841255.69     10264353.11      2841445.00     10263534.00
      2841355.67     10263303.08
#Sta/Elev= 30
  4159.3 1034.75  4220.8 1030.16  4292.7 1026.64  4456.9 1022.38  4492.6 1022.82
  4498.0 1024.30  4528.8 1023.63  4682.7 1023.64  4744.3 1024.76  4867.5 1024.37
  4908.5 1025.23  4929.1 1024.25  4949.6 1022.14  4959.9 1020.23  4970.1 1016.74
  4973.8 1014.61  4974.3 1014.11  4982.3 1014.61  5003.2 1015.48  5022.4 1017.89
  5063.7 1019.52  5086.7 1021.72  5118.2 1023.24  5123.5 1022.79  5148.1 1025.01
  5153.5 1024.55  5183.4 1027.11  5194.0 1029.04  5226.1 1030.43  5247.6 1032.26
#Mann=3,-1,0
  4159.3    0.05       0  4973.8    0.05       0  4982.3    0.05       0
Bank Sta=4973.8,4982.3
Exp/Cntr=0.3,0.1

Type RM Length L Ch R = 1,4406,583,583,583
BEGIN DESCRIPTION:
LITTLE LLANO 052 9.0
END DESCRIPTION:
XS GIS Cut Line= 3
      2842105.67     10264103.06      2841908.75     10263428.00
      2841355.71     10263003.13
#Sta/Elev= 30
  4296.8 1032.35  4335.1 1030.41  4385.7 1026.52  4463.4 1023.06  4646.0 1017.38
  4669.1 1016.71  4741.3 1021.31  4818.7 1019.26  4869.7 1020.34  4885.6 1018.47
  4963.4 1016.96  4984.3 1015.30  4991.3 1013.08  5009.0 1012.42  5009.5 1011.92
  5017.5 1012.42  5019.5 1013.55  5027.7 1014.61  5034.0 1017.07  5048.5 1017.08
  5054.8 1019.81  5063.0 1019.67  5069.3 1021.44  5155.2 1021.25  5470.0 1029.19
  5497.1 1028.04  5519.8 1029.34  5576.0 1028.03  5590.5 1029.44  5697.4 1030.57
#Mann=5,-1,0
  4296.8    0.05       0  4335.1    0.12       0  4646.0    0.05       0
  5009.0    0.03       0  5017.5    0.05       0
Bank Sta=5009,5017.5
Exp/Cntr=0.3,0.1

Type RM Length L Ch R = 1,3823,193,193,193
BEGIN DESCRIPTION:
LITTLE LLANO 052 8.0
END DESCRIPTION:
XS GIS Cut Line= 3
      2842561.64     10263719.05      2842356.41     10263441.38
      2841555.69     10262653.12
#Sta/Elev= 30
  4741.8 1035.59  4774.9 1035.51  4793.3 1036.53  4864.3 1035.48  4878.9 1033.68
  4901.0 1028.50  4914.4 1024.89  4922.8 1023.75  4943.6 1016.73  4979.1 1014.23
  4993.7 1010.91  5010.2 1010.41  5010.7 1009.91  5019.0 1010.41  5029.2 1013.52
  5043.8 1015.10  5079.3 1015.30  5114.7 1017.16  5121.7 1018.47  5135.9 1019.42
  5178.3 1020.33  5454.0 1018.71  5722.8 1019.03  5934.9 1021.40  6041.0 1023.81
  6055.2 1024.46  6069.3 1026.30  6083.5 1024.86  6111.7 1026.99  6210.7 1033.47
#Mann=6,-1,0
  4741.8    0.05       0  4774.9    0.12       0  4901.0    0.05       0
  5010.2    0.05       0  5019.0    0.05       0  6111.7    0.12       0
Bank Sta=5010.2,5019
Exp/Cntr=0.3,0.1

Type RM Length L Ch R = 1,3630,371,371,371
BEGIN DESCRIPTION:
LITTLE LLANO 052 7.0
END DESCRIPTION:
XS GIS Cut Line= 3
      2842655.71     10263503.14      2842578.00     10263420.00
      2841555.68     10262603.11
#Sta/Elev= 30
  4886.2 1034.95  4914.3 1031.56  4928.5 1028.73  4942.7 1022.98  4950.0 1018.69
  4956.8 1016.49  4985.2 1012.82  4991.7 1010.73  5009.8 1009.84  5010.3 1009.34
  5018.6 1009.84  5020.6 1011.14  5035.0 1013.68  5055.8 1014.83  5119.9 1014.97
  5169.5 1020.27  5454.5 1017.71  5917.2 1020.13  6002.0 1022.71  6074.1 1023.54
  6102.9 1025.84  6109.3 1027.56  6123.7 1025.38  6138.1 1025.71  6199.0 1030.06
  6214.9 1031.31  6258.2 1035.18  6272.6 1034.80  6287.0 1037.15  6308.6 1036.64
#Mann=6,-1,0
  4886.2    0.12       0  4991.7    0.05       0  5009.8    0.05       0
  5018.6    0.05       0  6199.0    0.12       0  6214.9    0.05       0
Bank Sta=5009.8,5018.6
Exp/Cntr=0.3,0.1

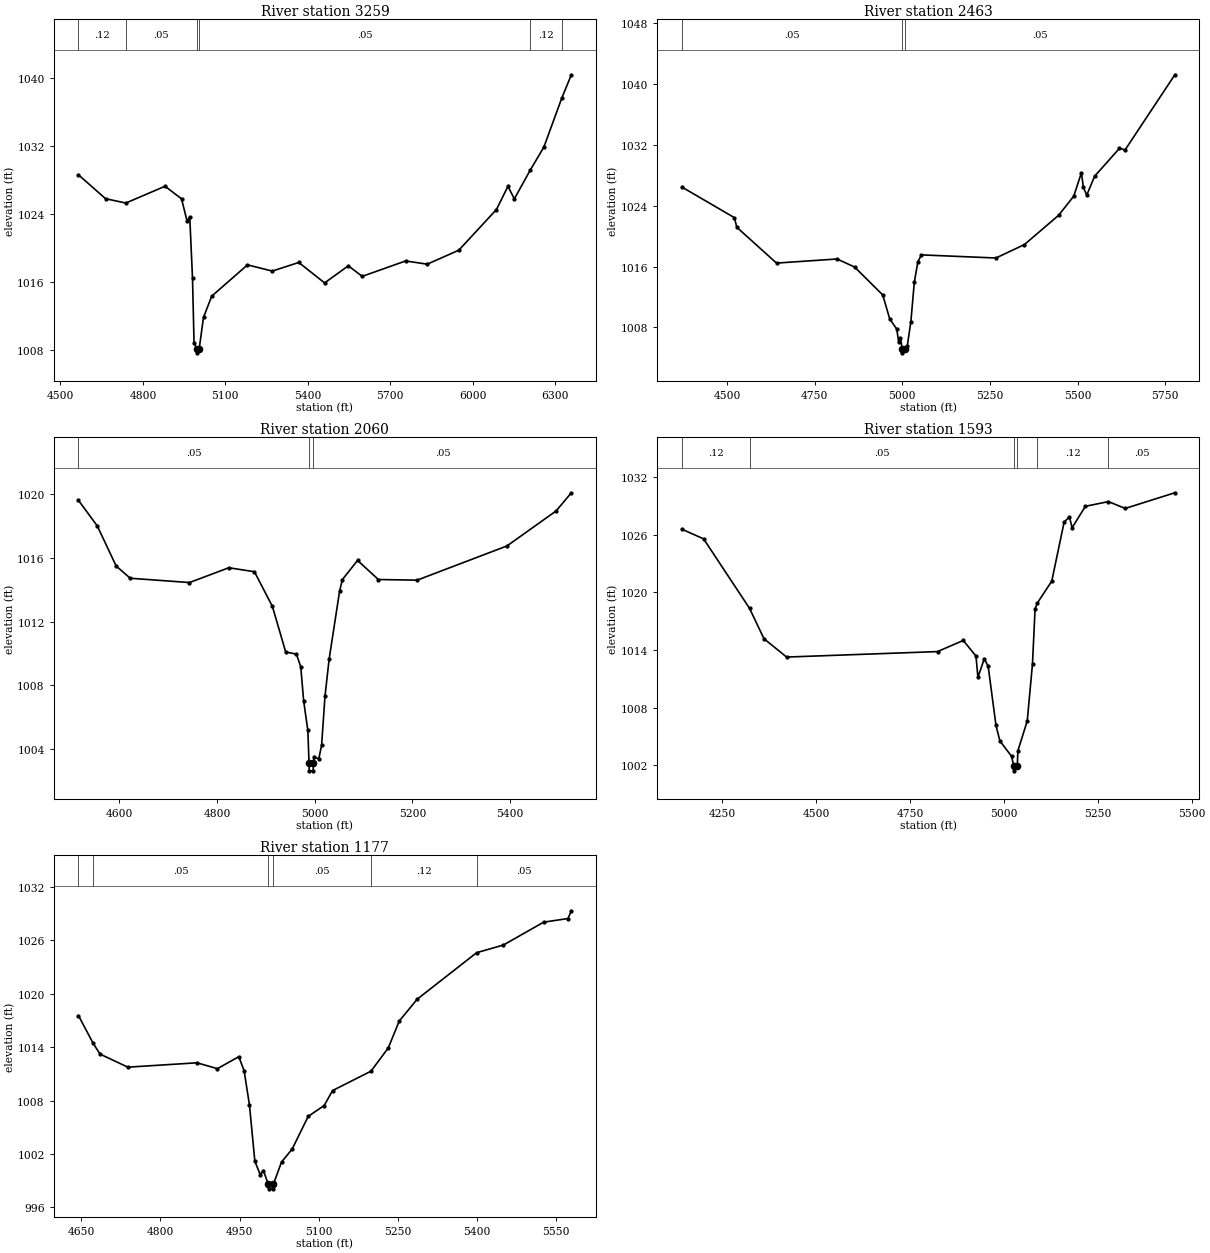
Type RM Length L Ch R = 1,3259,796,796,796
BEGIN DESCRIPTION:
LITTLE LLANO 052 6.0
END DESCRIPTION:
XS GIS Cut Line= 4
      2843137.22     10263320.68      2842964.13     10263131.49
      2842417.38     10263120.29      2841605.70     10262553.12
#Sta/Elev= 30
  4565.5 1028.61  4664.0 1025.81  4737.7 1025.30  4880.4 1027.27  4940.4 1025.80
  4960.4 1023.21  4970.4 1023.63  4980.4 1016.49  4986.0 1008.85  4996.0 1008.21
  4996.5 1007.71  5004.8 1008.21  5020.4 1011.87  5050.4 1014.37  5180.5 1018.04
  5270.5 1017.31  5367.1 1018.32  5461.1 1015.92  5547.5 1017.93  5598.1 1016.69
  5755.9 1018.50  5834.4 1018.12  5949.5 1019.76  6086.5 1024.54  6128.3 1027.26
  6151.6 1025.79  6209.0 1029.14  6259.2 1031.88  6324.3 1037.63  6359.0 1040.36
#Mann=6,-1,0
  4565.5    0.12       0  4737.7    0.05       0  4996.0    0.03       0
  5004.8    0.05       0  6209.0    0.12       0  6324.3    0.05       0
Bank Sta=4996,5004.8
Exp/Cntr=0.3,0.1

Type RM Length L Ch R = 1,2463,403,403,403
BEGIN DESCRIPTION:
Mapping XS 1b2ec0c3
END DESCRIPTION:
XS GIS Cut Line= 4
      2842875.58     10262974.51      2842646.18     10262749.14
      2842143.10     10262781.34      2841635.99     10262499.62
#Sta/Elev= 30
  4371.5 1026.46  4520.9 1022.44  4527.9 1021.17  4641.1 1016.46  4813.8 1017.00
  4863.9 1015.94  4944.1 1012.27  4964.1 1009.10  4984.2 1007.77  4989.6 1006.05
  4994.6 1006.63  4999.7 1005.15  5000.2 1004.65  5008.7 1005.15  5014.2 1005.58
  5024.3 1008.75  5034.3 1013.99  5044.3 1016.62  5054.3 1017.54  5267.1 1017.13
  5348.3 1018.90  5445.6 1022.74  5489.0 1025.27  5510.8 1028.35  5516.5 1026.41
  5526.0 1025.40  5548.5 1027.89  5619.4 1031.56  5635.5 1031.36  5777.3 1041.24
#Mann=3,-1,0
  4371.5    0.05       0  4999.7    0.05       0  5008.7    0.05       0
Bank Sta=4999.7,5008.7
Exp/Cntr=0.3,0.1

Type RM Length L Ch R = 1,2060,467,467,467
BEGIN DESCRIPTION:
LITTLE LLANO 052 5.0
END DESCRIPTION:
XS GIS Cut Line= 3
      2842815.22     10262817.56      2842655.68     10262503.11
      2842094.81     10262161.55
#Sta/Elev= 30
  4516.1 1019.62  4554.7 1018.01  4593.2 1015.50  4622.0 1014.73  4743.4 1014.46
  4823.9 1015.39  4876.4 1015.14  4913.2 1012.96  4940.4 1010.10  4962.4 1009.96
  4971.3 1009.17  4977.2 1007.02  4985.8 1005.17  4988.2 1003.13  4988.7 1002.63
  4996.7 1002.63  4997.2 1003.13  4998.5 1003.53  5008.1 1003.37  5014.0 1004.25
  5020.9 1007.32  5029.4 1009.65  5050.8 1013.92  5056.6 1014.65  5087.6 1015.85
  5130.2 1014.65  5209.6 1014.61  5393.6 1016.76  5494.3 1018.96  5525.4 1020.10
#Mann=3,-1,0
  4516.1    0.05       0  4988.2    0.03       0  4997.2    0.05       0
Bank Sta=4988.2,4997.2
Exp/Cntr=0.3,0.1

Type RM Length L Ch R = 1,1593,416,416,416
BEGIN DESCRIPTION:
LITTLE LLANO 052 4.0
END DESCRIPTION:
XS GIS Cut Line= 4
      2842891.68     10262970.47      2842823.27     10262286.31
      2842903.99     10262004.81      2843140.94     10261771.43
#Sta/Elev= 30
  4142.2 1026.57  4199.8 1025.57  4322.2 1018.33  4360.6 1015.17  4420.9 1013.26
  4822.9 1013.83  4891.6 1014.99  4925.4 1013.36  4930.6 1011.15  4947.5 1013.08
  4957.9 1012.30  4978.7 1006.14  4989.1 1004.53  5020.4 1002.91  5026.0 1001.91
  5026.5 1001.41  5035.5 1001.91  5037.0 1003.49  5062.0 1006.61  5076.0 1012.58
  5082.8 1018.25  5088.6 1018.87  5127.3 1021.17  5160.4 1027.34  5174.5 1027.84
  5181.5 1026.73  5216.9 1028.96  5278.2 1029.45  5323.0 1028.74  5455.2 1030.37
#Mann=6,-1,0
  4142.2    0.12       0  4322.2    0.05       0  5026.0    0.05       0
  5035.5    0.05       0  5088.6    0.12       0  5278.2    0.05       0
Bank Sta=5026,5035.5
Exp/Cntr=0.3,0.1

Type RM Length L Ch R = 1,1177,396,396,396
BEGIN DESCRIPTION:
LITTLE LLANO 052 3.0
END DESCRIPTION:
XS GIS Cut Line= 3
      2843076.82     10262793.44      2843165.36     10262221.91
      2843253.61     10261876.97
#Sta/Elev= 30
  4644.6 1017.54  4672.4 1014.43  4685.4 1013.22  4738.1 1011.75  4869.2 1012.24
  4908.0 1011.58  4948.5 1012.93  4958.6 1011.35  4968.8 1007.47  4978.9 1001.20
  4989.0  999.69  4995.2 1000.14  5004.4  998.58  5004.9  998.08  5013.5  998.08
  5014.0  998.58  5029.5 1001.09  5049.7 1002.55  5080.1 1006.22  5110.4 1007.44
  5126.3 1009.12  5199.2 1011.30  5232.0 1013.92  5252.7 1016.93  5286.8 1019.39
  5399.4 1024.61  5450.1 1025.47  5526.5 1028.04  5572.7 1028.45  5579.0 1029.32
#Mann=6,-1,0
  4644.6    0.12       0  4672.4    0.05       0  5004.4    0.03       0
  5014.0    0.05       0  5199.2    0.12       0  5399.4    0.05       0
Bank Sta=5004.4,5014
Exp/Cntr=0.3,0.1