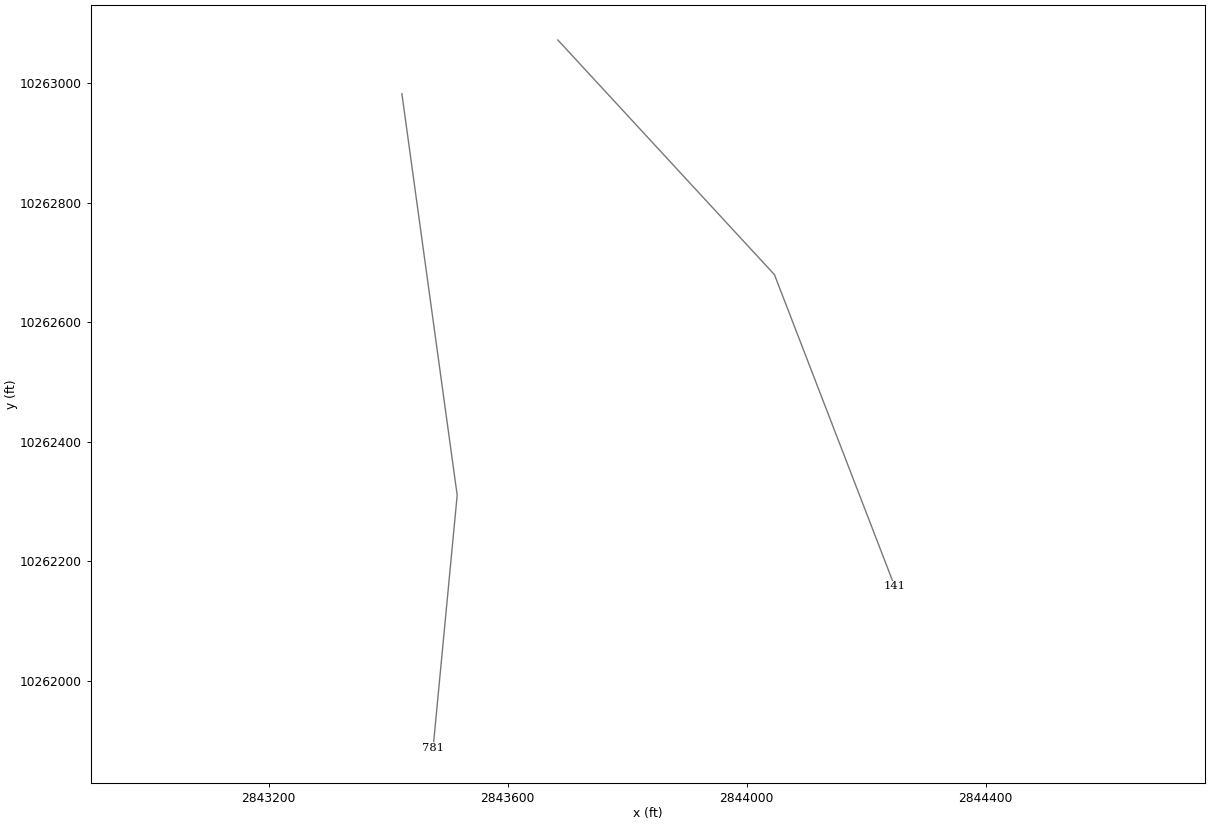
HEC-RAS study LITTLE LLANO 052.prj: LITTLE LLANO 052 Base Level Engineering

--- LITTLE LLANO 052.g01 (geometry) --- (continued)

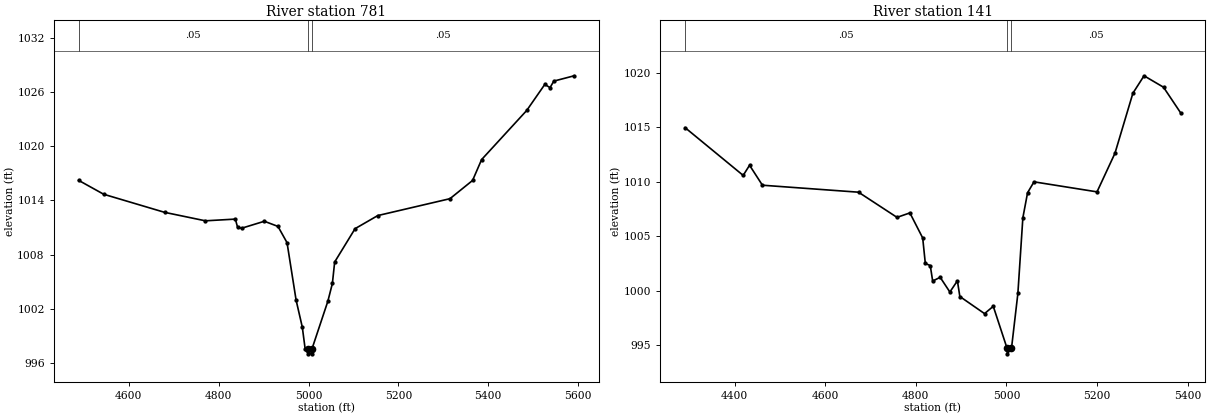
Type RM Length L Ch R = 1,781,640,640,640
BEGIN DESCRIPTION:
LITTLE LLANO 052 2.0
END DESCRIPTION:
XS GIS Cut Line= 3
      2843422.94     10262982.55      2843515.51     10262310.46
      2843475.27     10261888.01
#Sta/Elev= 30
  4488.3 1016.22  4544.1 1014.68  4679.5 1012.68  4770.4 1011.74  4837.1 1011.93
  4842.1 1011.01  4851.1 1010.92  4901.6 1011.69  4931.9 1011.12  4952.1 1009.32
  4972.3 1002.95  4986.1  999.96  4992.5  997.52  4997.7  997.51  4998.2  997.01
  5006.8  997.01  5007.3  997.51  5042.9 1002.83  5053.0 1004.80  5058.1 1007.18
  5103.5 1010.87  5154.0 1012.32  5314.7 1014.19  5365.0 1016.21  5385.1 1018.52
  5485.5 1023.96  5525.7 1026.84  5537.4 1026.49  5545.8 1027.21  5591.1 1027.80
#Mann=3,-1,0
  4488.3    0.05       0  4997.7    0.03       0  5007.3    0.05       0
Bank Sta=4997.7,5007.3
Exp/Cntr=0.3,0.1

Type RM Length L Ch R = 1,141,0,0,0
BEGIN DESCRIPTION:
LITTLE LLANO 052 1.0
END DESCRIPTION:
XS GIS Cut Line= 3
      2843683.95     10263072.49      2844046.59     10262679.63
      2844247.87     10262157.85
#Sta/Elev= 30
  4290.7 1014.97  4418.9 1010.59  4433.0 1011.52  4461.4 1009.69  4673.5 1009.05
  4758.5 1006.74  4786.9 1007.15  4815.2 1004.85  4821.0 1002.51  4831.9 1002.32
  4837.2 1000.90  4853.8 1001.24  4875.2  999.89  4891.8 1000.92  4897.2  999.48
  4951.7  997.91  4971.0  998.58  5001.5  994.72  5002.0  994.22  5011.2  994.72
  5025.3  999.76  5036.3 1006.70  5046.7 1009.00  5060.9 1010.00  5200.0 1009.08
  5239.6 1012.62  5279.2 1018.13  5303.8 1019.73  5346.8 1018.68  5384.6 1016.33
#Mann=3,-1,0
  4290.7    0.05       0  5001.5    0.05       0  5011.2    0.05       0
Bank Sta=5001.5,5011.2
Exp/Cntr=0.3,0.1

Chan Stop Cuts=-1