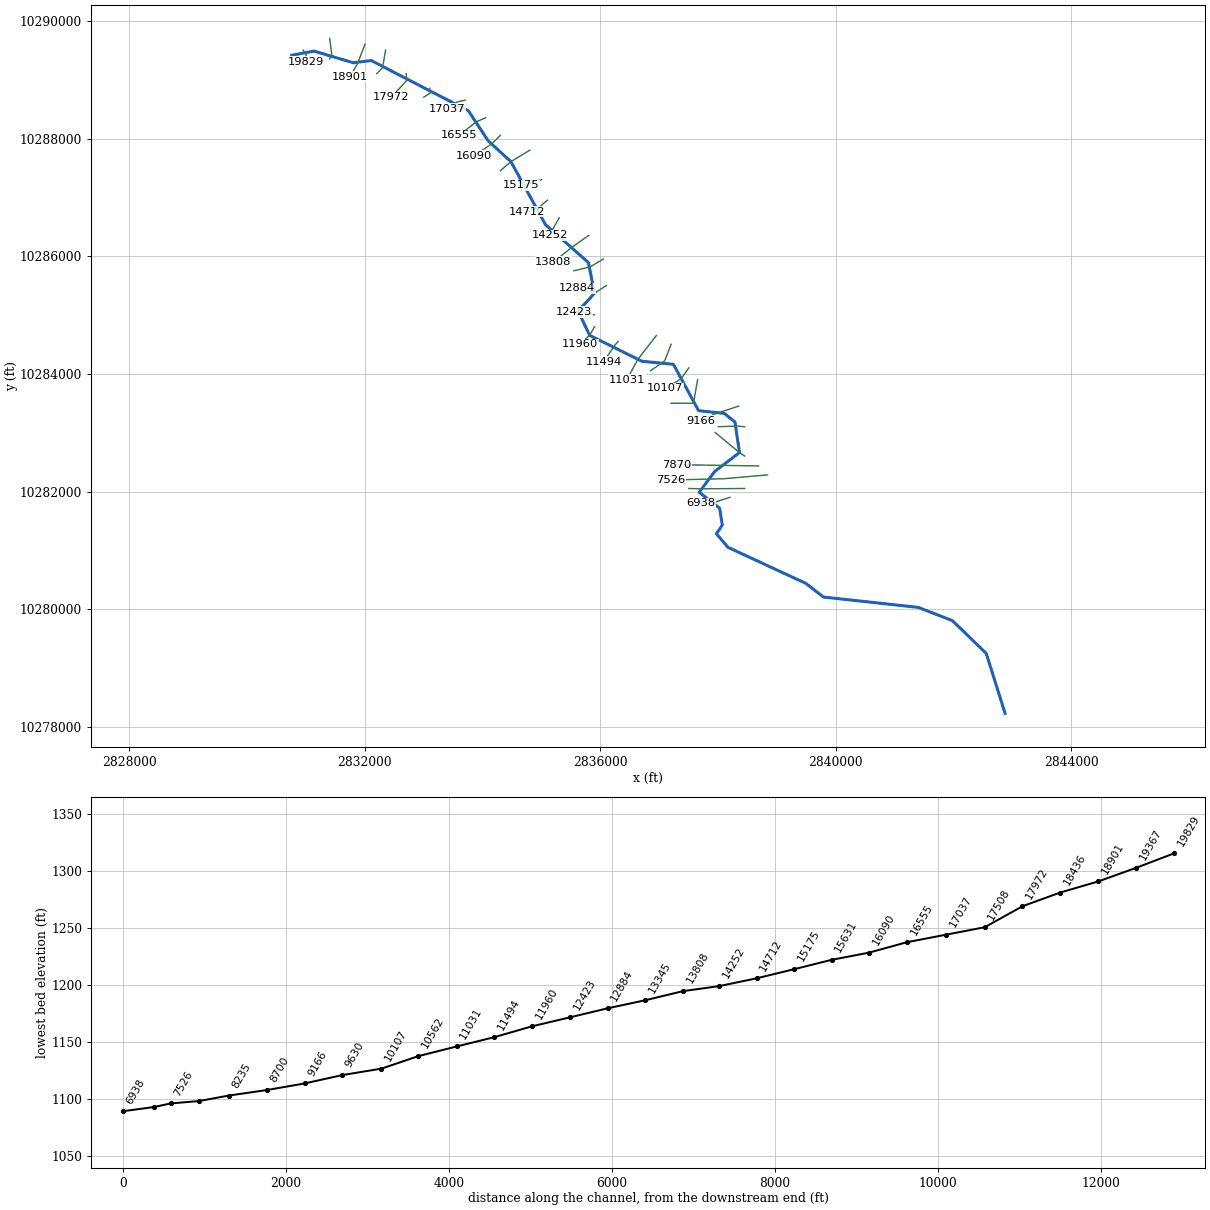
--- LITTLE LLANO 055.prj (project) ---

Proj Title=LITTLE LLANO 055 Base Level Engineering
Current Plan=p01
Default Exp/Contr=0.3,0.1
English Units
Geom File=g01
Flow File=f01
Plan File=p01
BEGIN DESCRIPTION:
LITTLE LLANO 055
END DESCRIPTION:

--- LITTLE LLANO 055.p01 (plan) ---

Plan Title=Multiple Run
Short Identifier=Multiple
Geom File=g01
Flow File=f01
Subcritical Flow
K Sum by GR= 0
Std Step Tol= 0.01
Critical Tol= 0.01
Num of Std Step Trials= 20
Max Error Tol= 0.3
Flow Tol Ratio= 0.001
Split Flow NTrial= 30
Split Flow Tol= 0.02
Split Flow Ratio= 0.02
Log Output Level= 0
Friction Slope Method= 1
Unsteady Friction Slope Method= 2
Unsteady Bridges Friction Slope Method= 1
Parabolic Critical Depth
Global Vel Dist=  1 , 1 , 1
Global Log Level= 0
CheckData=True
Encroach Param= -1, 0, 0, 0
BEGIN DESCRIPTION:
Multiple Run
END DESCRIPTION:

--- LITTLE LLANO 055.f01 (steady flow) ---

Flow Title=Multiple
Number of Profiles=7
Profile Names=10-year,25-year,50-year,1pct_min,100-year,1pct_plu,500-year
River Rch & RM= LITTLE LLANO 055,Reach-1,19829
     403     647    1407    1165    1982    3374    2896
River Rch & RM= LITTLE LLANO 055,Reach-1,11960
     659    1109    1572    1079    2154    4299    3019
River Rch & RM= LITTLE LLANO 055,Reach-1,6015
    1401    2445    4123    2931    5833   11609    8112
Boundary for River Rch & Prof#=LITTLE LLANO 055,Reach-1,1
Up Type=0
Dn Type=3
Dn Slope=0.005
Boundary for River Rch & Prof#=LITTLE LLANO 055,Reach-1,2
Up Type=0
Dn Type=3
Dn Slope=0.005
Boundary for River Rch & Prof#=LITTLE LLANO 055,Reach-1,3
Up Type=0
Dn Type=3
Dn Slope=0.005
Boundary for River Rch & Prof#=LITTLE LLANO 055,Reach-1,4
Up Type=0
Dn Type=3
Dn Slope=0.005
Boundary for River Rch & Prof#=LITTLE LLANO 055,Reach-1,5
Up Type=0
Dn Type=3
Dn Slope=0.005
Boundary for River Rch & Prof#=LITTLE LLANO 055,Reach-1,6
Up Type=0
Dn Type=3
Dn Slope=0.005
Boundary for River Rch & Prof#=LITTLE LLANO 055,Reach-1,7
Up Type=0
Dn Type=3
Dn Slope=0.005

--- LITTLE LLANO 055.g01 (geometry) ---

Geom Title=Existing Conditions

River Reach=LITTLE LLANO 055,Reach-1
Reach XY= 30
      2830762.50     10289416.00      2831141.00     10289486.00
      2831807.75     10289288.00      2832113.25     10289326.00
      2833762.50     10288472.00      2834099.25     10287961.00
      2834484.75     10287607.00      2835071.50     10286538.00
      2835800.75     10285892.00      2835904.75     10285371.00
      2835627.00     10285069.00      2835821.50     10284656.00
      2836710.50     10284215.00      2837245.25     10284163.00
      2837672.25     10283375.00      2838109.75     10283329.00
      2838290.25     10283183.00      2838366.75     10282663.00
      2837946.50     10282343.00      2837682.75     10281989.00
      2838029.75     10281718.00      2838075.00     10281430.00
      2837974.50     10281285.00      2838171.75     10281053.00
      2839492.00     10280441.00      2839794.00     10280208.00
      2841403.75     10280032.00      2841985.00     10279806.00
      2842558.75     10279249.00      2842877.75     10278231.00

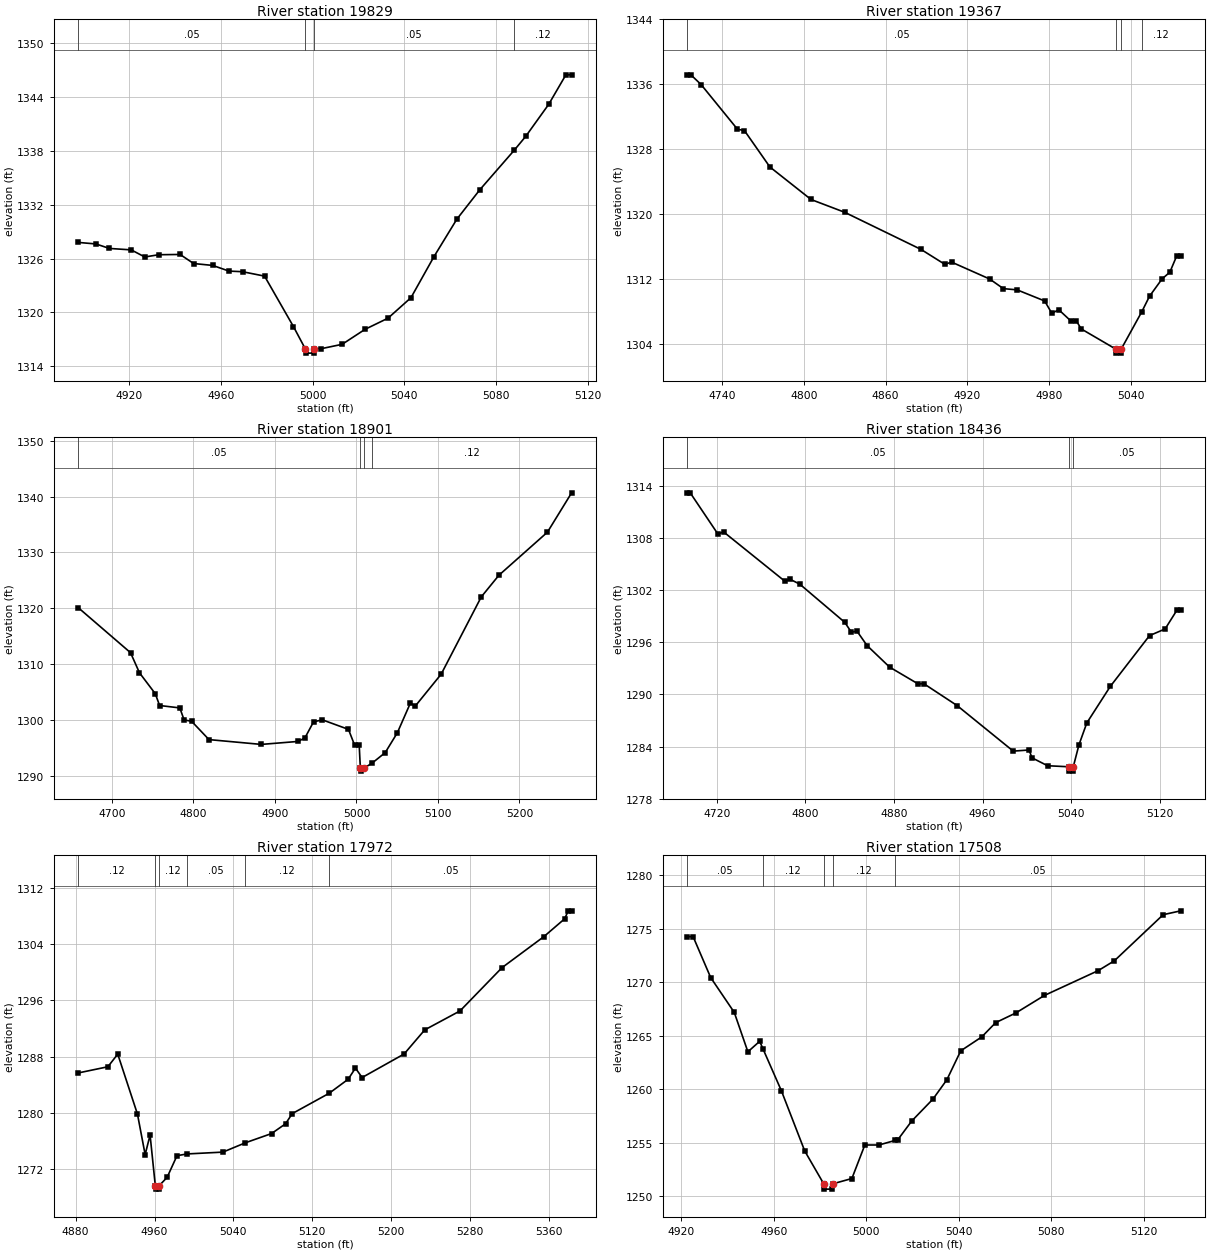
Type RM Length L Ch R = 1,19829,462,462,462
BEGIN DESCRIPTION:
LITTLE LLANO 055 39.0
END DESCRIPTION:
XS GIS Cut Line= 3
      2830955.70     10289503.08      2831009.00     10289416.00
      2831005.69     10289303.15
#Sta/Elev= 30
  4897.9 1327.79  4905.6 1327.62  4911.5 1327.12  4921.0 1326.96  4926.9 1326.17
  4933.0 1326.42  4942.3 1326.45  4948.2 1325.44  4956.5 1325.23  4963.6 1324.60
  4969.5 1324.53  4979.1 1324.04  4991.7 1318.42  4996.8 1315.97  4997.0 1315.47
  5000.5 1315.47  5000.8 1315.97  5003.9 1315.97  5012.9 1316.45  5022.9 1318.12
  5032.9 1319.36  5042.9 1321.64  5052.9 1326.20  5062.9 1330.38  5072.9 1333.65
  5087.8 1338.02  5092.9 1339.59  5102.9 1343.15  5110.4 1346.44  5112.9 1346.44
#Mann=4,-1,0
  4897.9    0.05       0  4996.8    0.05       0  5000.8    0.05       0
  5087.8    0.12       0
Bank Sta=4996.8,5000.8
Exp/Cntr=0.3,0.1

Type RM Length L Ch R = 1,19367,466,466,466
BEGIN DESCRIPTION:
LITTLE LLANO 055 38.0
END DESCRIPTION:
XS GIS Cut Line= 3
      2831405.68     10289703.15      2831443.00     10289420.00
      2831405.68     10289353.11
#Sta/Elev= 30
  4714.4 1337.16  4717.0 1337.16  4724.5 1335.96  4751.2 1330.45  4756.3 1330.29
  4775.0 1325.80  4805.2 1321.79  4829.8 1320.22  4885.9 1315.64  4903.4 1313.80
  4908.4 1314.07  4936.3 1311.99  4946.4 1310.80  4956.5 1310.65  4976.7 1309.28
  4982.0 1307.75  4987.0 1308.21  4995.9 1306.82  5000.0 1306.82  5003.5 1305.84
  5028.9 1303.35  5029.1 1302.85  5032.6 1302.85  5032.9 1303.35  5048.0 1307.95
  5053.7 1309.87  5062.9 1312.00  5068.6 1312.83  5073.7 1314.86  5076.6 1314.86
#Mann=4,-1,0
  4714.4    0.05       0  5028.9    0.03       0  5032.9    0.05       0
  5048.0    0.12       0
Bank Sta=5028.9,5032.9
Exp/Cntr=0.3,0.1

Type RM Length L Ch R = 1,18901,465,465,465
BEGIN DESCRIPTION:
LITTLE LLANO 055 37.0
END DESCRIPTION:
XS GIS Cut Line= 3
      2832005.68     10289603.09      2831884.00     10289284.00
      2831755.71     10289053.15
#Sta/Elev= 30
  4658.5 1320.12  4722.7 1312.06  4733.7 1308.46  4753.1 1304.72  4758.4 1302.61
  4783.2 1302.18  4788.5 1300.02  4797.6 1299.80  4819.0 1296.51  4883.2 1295.65
  4928.2 1296.18  4936.7 1296.80  4947.4 1299.70  4958.3 1300.04  4990.2 1298.34
  4997.8 1295.50  5003.4 1295.50  5004.8 1291.37  5005.0 1290.87  5008.8 1291.37
  5019.2 1292.30  5035.3 1294.18  5050.2 1297.73  5066.3 1303.08  5072.0 1302.47
  5104.0 1308.22  5153.2 1322.04  5174.9 1325.92  5234.4 1333.62  5264.1 1340.66
#Mann=4,-1,0
  4658.5    0.05       0  5004.8    0.05       0  5008.8    0.05       0
  5019.2    0.12       0
Bank Sta=5004.8,5008.8
Exp/Cntr=0.3,0.1

Type RM Length L Ch R = 1,18436,464,464,464
BEGIN DESCRIPTION:
LITTLE LLANO 055 36.0
END DESCRIPTION:
XS GIS Cut Line= 3
      2832355.69     10289503.15      2832304.25     10289201.00
      2832205.69     10289103.12
#Sta/Elev= 30
  4693.5 1313.17  4696.1 1313.17  4721.1 1308.43  4726.2 1308.68  4781.3 1303.03
  4786.4 1303.22  4795.0 1302.67  4835.6 1298.28  4841.6 1297.14  4846.6 1297.27
  4855.8 1295.60  4876.1 1293.13  4901.8 1291.20  4906.9 1291.23  4937.0 1288.71
  4987.7 1283.47  5002.0 1283.60  5004.6 1282.70  5018.7 1281.79  5037.9 1281.67
  5038.2 1281.17  5041.7 1281.17  5041.9 1281.67  5047.0 1284.19  5054.1 1286.71
  5075.3 1290.91  5110.7 1296.75  5124.8 1297.52  5135.4 1299.67  5138.9 1299.67
#Mann=3,-1,0
  4693.5    0.05       0  5037.9    0.03       0  5041.9    0.05       0
Bank Sta=5037.9,5041.9
Exp/Cntr=0.3,0.1

Type RM Length L Ch R = 1,17972,464,464,464
BEGIN DESCRIPTION:
LITTLE LLANO 055 35.0
END DESCRIPTION:
XS GIS Cut Line= 3
      2832705.68     10289103.11      2832714.00     10288986.00
      2832455.67     10288703.10
#Sta/Elev= 30
  4882.6 1285.67  4912.7 1286.55  4922.7 1288.35  4942.7 1279.81  4950.5 1274.04
  4955.5 1276.84  4960.8 1269.63  4961.0 1269.13  4964.5 1269.13  4964.8 1269.63
  4972.8 1270.81  4982.8 1273.89  4993.1 1274.14  5029.4 1274.40  5052.2 1275.73
  5078.7 1277.04  5092.9 1278.43  5099.7 1279.88  5137.1 1282.77  5156.4 1284.77
  5163.8 1286.36  5170.6 1285.02  5213.2 1288.37  5234.1 1291.80  5269.9 1294.50
  5312.5 1300.66  5355.0 1305.08  5376.0 1307.61  5379.7 1308.75  5383.1 1308.75
#Mann=6,-1,0
  4882.6    0.12       0  4960.8    0.05       0  4964.8    0.12       0
  4993.1    0.05       0  5052.2    0.12       0  5137.1    0.05       0
Bank Sta=4960.8,4964.8
Exp/Cntr=0.3,0.1

Type RM Length L Ch R = 1,17508,471,471,471
BEGIN DESCRIPTION:
LITTLE LLANO 055 34.0
END DESCRIPTION:
XS GIS Cut Line= 3
      2833105.69     10288853.07      2833120.00     10288777.00
      2833005.70     10288703.12
#Sta/Elev= 30
  4922.6 1274.24  4925.1 1274.24  4932.7 1270.42  4942.9 1267.17  4948.8 1263.49
  4953.9 1264.47  4955.3 1263.78  4963.3 1259.85  4973.4 1254.23  4981.6 1251.17
  4981.9 1250.67  4985.4 1250.67  4985.6 1251.17  4993.8 1251.66  4999.4 1254.79
  5005.5 1254.79  5012.4 1255.21  5013.7 1255.29  5019.7 1257.03  5028.9 1259.08
  5034.9 1260.88  5040.9 1263.58  5050.0 1264.88  5056.0 1266.21  5064.7 1267.11
  5077.1 1268.75  5100.4 1271.07  5107.4 1271.99  5128.5 1276.29  5136.1 1276.65
#Mann=5,-1,0
  4922.6    0.05       0  4955.3    0.12       0  4981.6    0.07       0
  4985.6    0.12       0  5012.4    0.05       0
Bank Sta=4981.6,4985.6
Exp/Cntr=0.3,0.1

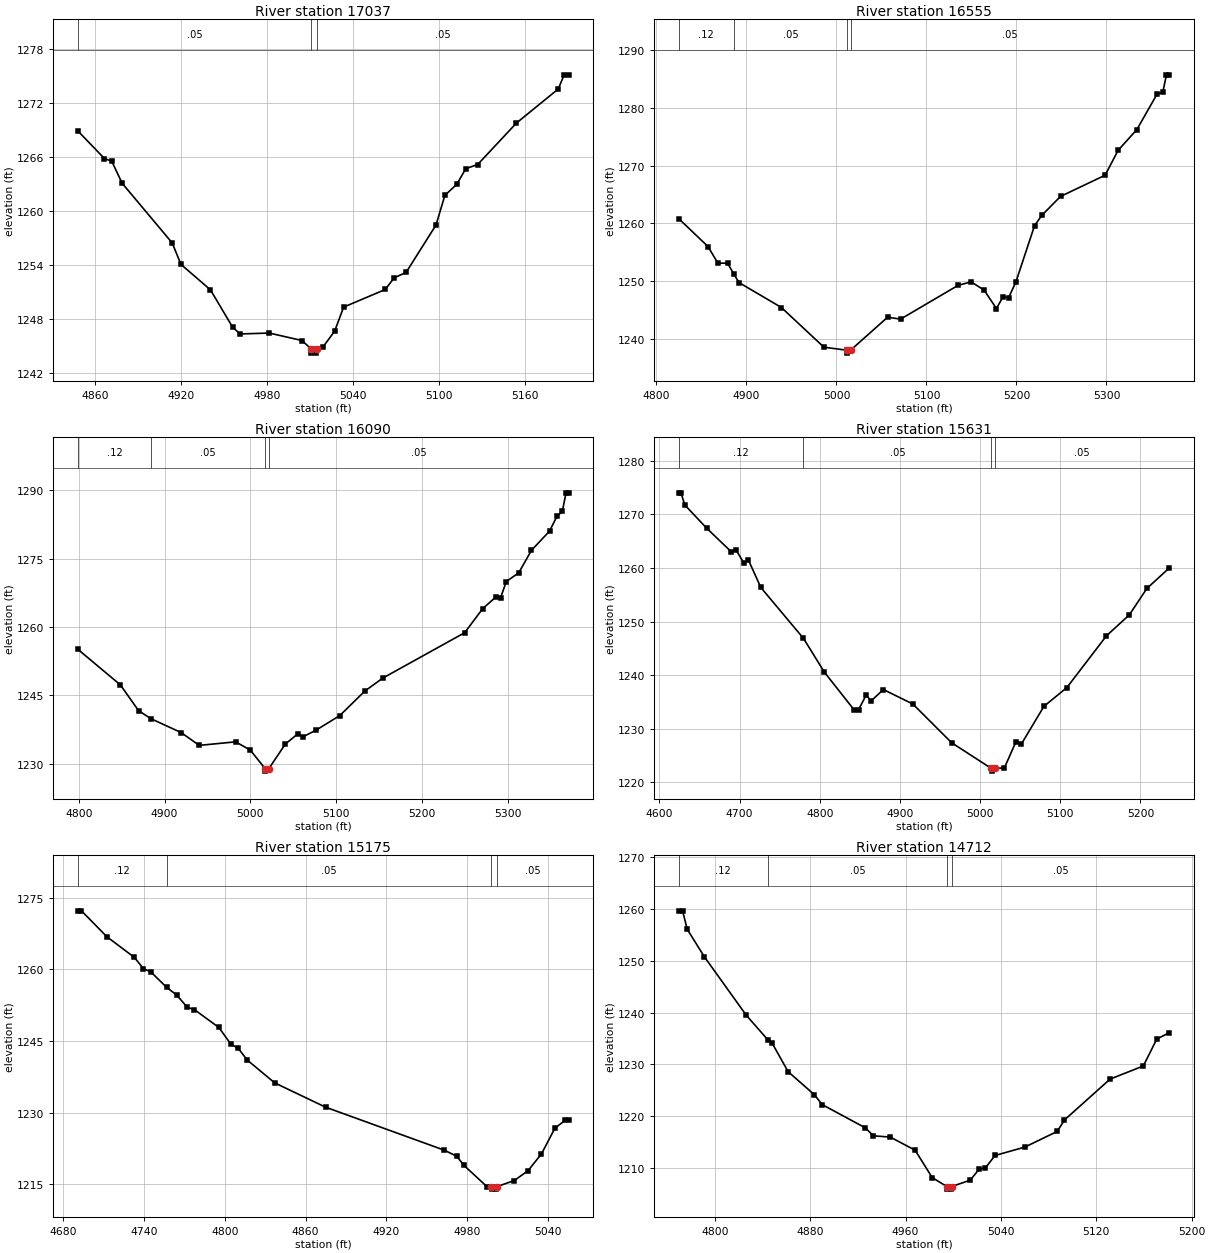
Type RM Length L Ch R = 1,17037,482,482,482
BEGIN DESCRIPTION:
LITTLE LLANO 055 33.0
END DESCRIPTION:
XS GIS Cut Line= 3
      2833705.64     10288653.10      2833557.75     10288618.00
      2833405.67     10288503.10
#Sta/Elev= 30
  4848.0 1268.87  4866.5 1265.81  4871.6 1265.52  4878.8 1263.08  4913.8 1256.44
  4919.9 1254.06  4940.5 1251.23  4956.0 1247.08  4961.2 1246.33  4981.6 1246.43
  5004.4 1245.60  5010.6 1244.70  5010.9 1244.20  5014.4 1244.20  5014.6 1244.70
  5018.9 1244.85  5027.2 1246.63  5033.5 1249.31  5062.6 1251.27  5068.8 1252.57
  5077.1 1253.16  5098.0 1258.43  5104.2 1261.73  5112.5 1262.95  5118.8 1264.69
  5127.1 1265.15  5154.2 1269.76  5183.3 1273.53  5187.5 1275.11  5190.6 1275.11
#Mann=3,-1,0
  4848.0    0.05       0  5010.6    0.05       0  5014.6    0.05       0
Bank Sta=5010.6,5014.6
Exp/Cntr=0.3,0.1

Type RM Length L Ch R = 1,16555,465,465,465
BEGIN DESCRIPTION:
LITTLE LLANO 055 32.0
END DESCRIPTION:
XS GIS Cut Line= 3
      2834055.71     10288353.12      2833894.50     10288284.00
      2833605.65     10288053.09
#Sta/Elev= 30
  4824.6 1260.84  4857.3 1255.98  4868.1 1253.14  4879.0 1253.10  4886.2 1251.17
  4891.7 1249.76  4938.8 1245.45  4986.0 1238.59  5011.6 1238.06  5011.8 1237.56
  5015.6 1238.06  5056.8 1243.77  5071.2 1243.44  5135.2 1249.29  5149.6 1249.88
  5164.0 1248.46  5177.7 1245.27  5184.9 1247.26  5191.3 1247.17  5199.3 1249.86
  5220.1 1259.62  5228.1 1261.38  5248.9 1264.66  5298.5 1268.33  5312.9 1272.63
  5333.7 1276.22  5356.2 1282.36  5362.6 1282.71  5366.6 1285.69  5369.8 1285.69
#Mann=4,-1,0
  4824.6    0.12       0  4886.2    0.05       0  5011.6    0.05       0
  5015.6    0.05       0
Bank Sta=5011.6,5015.6
Exp/Cntr=0.3,0.1

Type RM Length L Ch R = 1,16090,459,459,459
BEGIN DESCRIPTION:
LITTLE LLANO 055 31.0
END DESCRIPTION:
XS GIS Cut Line= 3
      2834305.71     10288053.13      2834161.75     10287913.00
      2833855.70     10287703.12
#Sta/Elev= 30
  4799.1 1255.08  4848.6 1247.30  4869.8 1241.65  4884.4 1239.88  4919.4 1236.86
  4940.5 1234.05  4982.9 1234.83  5000.0 1233.02  5017.5 1228.91  5017.7 1228.41
  5021.5 1228.91  5040.8 1234.33  5055.7 1236.62  5061.8 1235.97  5076.7 1237.39
  5104.4 1240.59  5133.5 1245.95  5154.5 1248.80  5249.9 1258.74  5271.0 1264.03
  5285.9 1266.50  5291.9 1266.45  5298.4 1269.95  5312.9 1271.85  5327.8 1276.80
  5348.8 1280.99  5357.6 1284.28  5363.7 1285.30  5368.1 1289.39  5371.1 1289.39
#Mann=4,-1,0
  4799.1    0.12       0  4884.4    0.05       0  5017.5    0.05       0
  5021.5    0.05       0
Bank Sta=5017.5,5021.5
Exp/Cntr=0.3,0.1

Type RM Length L Ch R = 1,15631,456,456,456
BEGIN DESCRIPTION:
LITTLE LLANO 055 30.0
END DESCRIPTION:
XS GIS Cut Line= 3
      2834805.68     10287803.11      2834484.75     10287607.00
      2834305.69     10287453.12
#Sta/Elev= 30
  4623.9 1274.04  4626.8 1274.04  4631.6 1271.77  4659.0 1267.42  4689.7 1263.02
  4695.5 1263.39  4705.1 1260.98  4711.0 1261.49  4726.4 1256.38  4779.6 1246.88
  4805.8 1240.55  4842.6 1233.57  4848.4 1233.58  4858.0 1236.31  4863.9 1235.17
  4879.3 1237.32  4916.1 1234.62  4964.6 1227.38  5014.1 1222.59  5014.3 1222.09
  5018.1 1222.59  5030.4 1222.71  5044.6 1227.53  5051.5 1227.14  5079.7 1234.19
  5108.3 1237.69  5157.7 1247.35  5186.2 1251.26  5208.1 1256.19  5236.1 1260.02
#Mann=4,-1,0
  4623.9    0.12       0  4779.6    0.05       0  5014.1    0.03       0
  5018.1    0.05       0
Bank Sta=5014.1,5018.1
Exp/Cntr=0.3,0.1

Type RM Length L Ch R = 1,15175,463,463,463
BEGIN DESCRIPTION:
LITTLE LLANO 055 29.0
END DESCRIPTION:
XS GIS Cut Line= 3
      2835005.66     10287303.11      2834710.50     10287211.00
      2834655.66     10287203.11
#Sta/Elev= 30
  4690.8 1272.26  4693.4 1272.26  4712.3 1266.83  4732.7 1262.51  4739.5 1260.13
  4744.8 1259.51  4756.7 1256.22  4764.1 1254.64  4772.0 1252.06  4777.3 1251.57
  4795.5 1247.82  4804.5 1244.30  4809.8 1243.49  4816.5 1241.02  4837.0 1236.21
  4874.8 1231.12  4963.1 1222.10  4972.3 1220.83  4977.5 1218.96  4994.6 1214.50
  4997.9 1214.45  4998.2 1213.95  5001.7 1213.95  5001.9 1214.45  5015.0 1215.75
  5025.2 1217.80  5035.2 1221.33  5045.3 1226.76  5052.9 1228.37  5055.4 1228.37
#Mann=4,-1,0
  4690.8    0.12       0  4756.7    0.05       0  4997.9    0.05       0
  5001.9    0.05       0
Bank Sta=4997.9,5001.9
Exp/Cntr=0.3,0.1

Type RM Length L Ch R = 1,14712,460,460,460
BEGIN DESCRIPTION:
LITTLE LLANO 055 28.0
END DESCRIPTION:
XS GIS Cut Line= 3
      2835105.71     10286953.14      2834929.25     10286805.00
      2834755.64     10286753.10
#Sta/Elev= 30
  4769.6 1259.67  4772.9 1259.67  4776.8 1256.11  4791.1 1250.82  4826.2 1239.54
  4844.5 1234.73  4848.0 1234.13  4861.4 1228.61  4883.5 1224.14  4890.0 1222.24
  4926.3 1217.74  4932.9 1216.21  4947.2 1215.96  4968.0 1213.42  4982.3 1208.14
  4994.6 1206.41  4994.9 1205.91  4998.4 1205.91  4998.6 1206.41  5014.2 1207.64
  5021.7 1209.77  5026.9 1210.00  5035.0 1212.41  5060.0 1214.03  5087.2 1217.06
  5093.2 1219.26  5131.5 1227.16  5159.4 1229.70  5170.7 1234.90  5181.2 1236.13
#Mann=4,-1,0
  4769.6    0.12       0  4844.5    0.05       0  4994.6    0.05       0
  4998.6    0.05       0
Bank Sta=4994.6,4998.6
Exp/Cntr=0.3,0.1

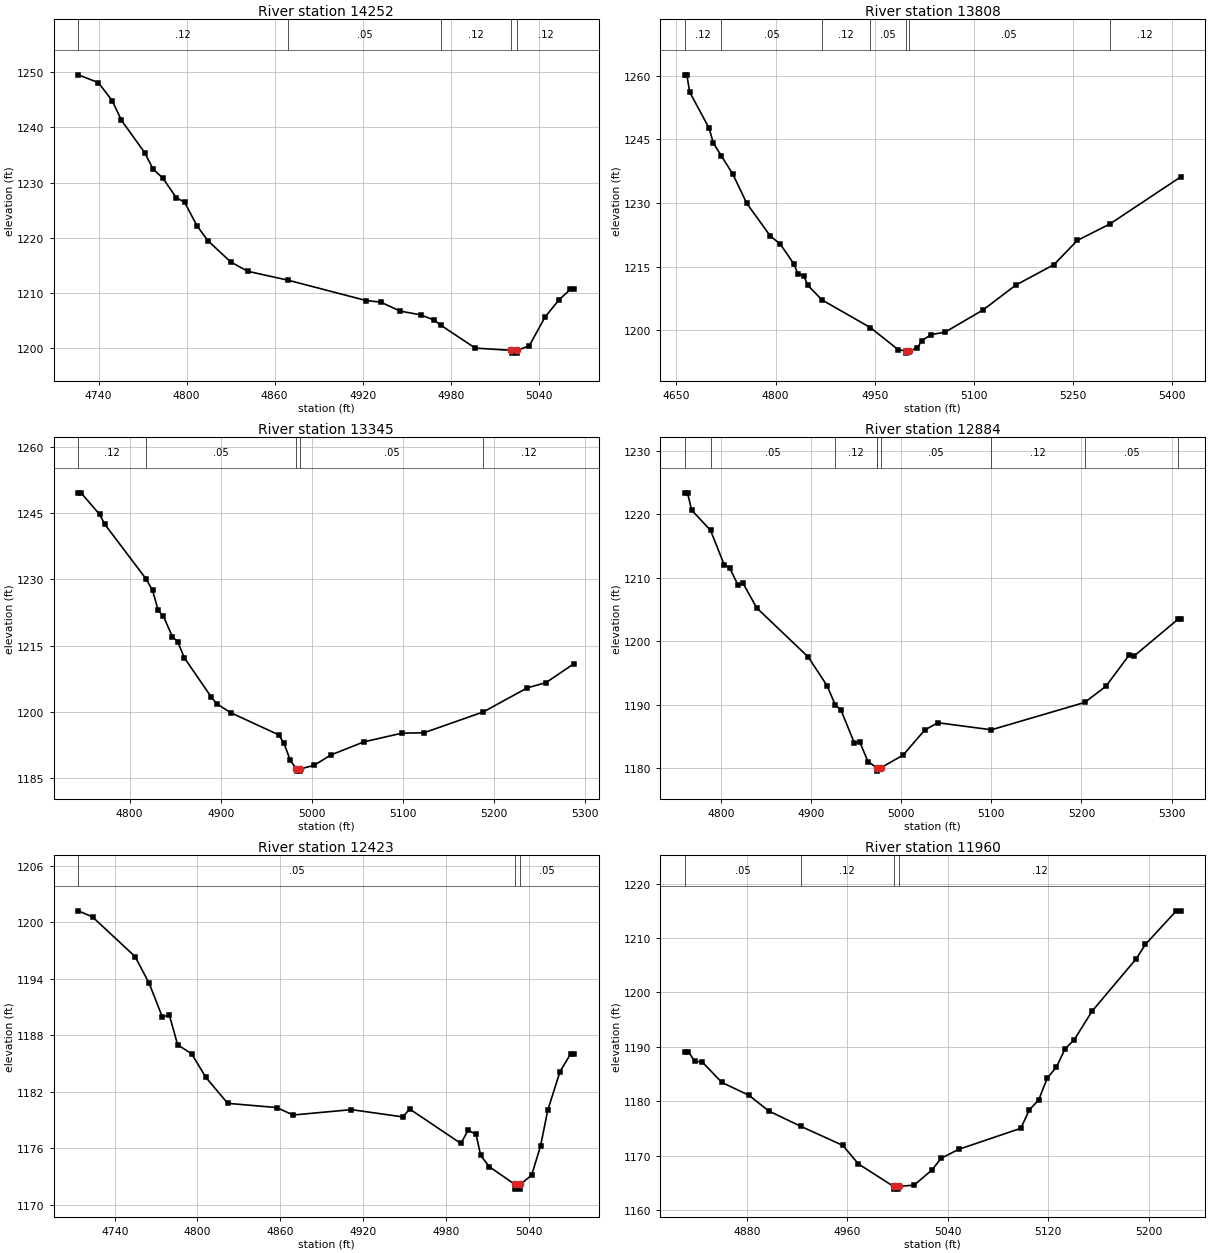
Type RM Length L Ch R = 1,14252,444,444,444
BEGIN DESCRIPTION:
LITTLE LLANO 055 27.0
END DESCRIPTION:
XS GIS Cut Line= 3
      2835305.68     10286653.10      2835168.75     10286416.00
      2835155.69     10286353.14
#Sta/Elev= 30
  4726.2 1249.56  4739.8 1248.15  4749.3 1244.87  4755.6 1241.30  4771.4 1235.44
  4777.2 1232.43  4783.9 1230.78  4792.9 1227.27  4798.7 1226.41  4807.0 1222.19
  4814.5 1219.46  4830.1 1215.58  4841.8 1213.89  4869.3 1212.27  4922.5 1208.58
  4932.2 1208.31  4945.6 1206.67  4959.5 1205.99  4968.7 1205.05  4973.1 1204.14
  4996.8 1199.95  5021.4 1199.54  5021.6 1199.04  5025.1 1199.04  5025.4 1199.54
  5033.6 1200.37  5044.3 1205.57  5054.0 1208.76  5061.7 1210.63  5064.2 1210.63
#Mann=5,-1,0
  4726.2    0.12       0  4869.3    0.05       0  4973.1    0.12       0
  5021.4    0.07       0  5025.4    0.12       0
Bank Sta=5021.4,5025.4
Exp/Cntr=0.3,0.1

Type RM Length L Ch R = 1,13808,463,463,463
BEGIN DESCRIPTION:
LITTLE LLANO 055 26.0
END DESCRIPTION:
XS GIS Cut Line= 3
      2835805.71     10286353.13      2835529.75     10286159.00
      2835205.69     10285903.12
#Sta/Elev= 30
  4662.6 1260.22  4665.7 1260.22  4670.0 1256.14  4699.3 1247.68  4705.8 1244.16
  4717.9 1241.13  4735.4 1236.78  4756.3 1229.95  4792.0 1222.24  4806.8 1220.39
  4827.7 1215.64  4833.8 1213.32  4842.5 1212.91  4848.6 1210.64  4870.2 1207.18
  4943.5 1200.65  4985.4 1195.47  4997.4 1195.14  4997.7 1194.64  5001.4 1195.14
  5014.6 1195.83  5020.9 1197.55  5035.4 1199.01  5056.2 1199.56  5113.9 1204.81
  5163.6 1210.68  5221.4 1215.51  5256.6 1221.20  5305.8 1225.07  5412.9 1236.15
#Mann=7,-1,0
  4662.6    0.12       0  4717.9    0.05       0  4870.2    0.12       0
  4943.5    0.05       0  4997.4    0.05       0  5001.4    0.05       0
  5305.8    0.12       0
Bank Sta=4997.4,5001.4
Exp/Cntr=0.3,0.1

Type RM Length L Ch R = 1,13345,461,461,461
BEGIN DESCRIPTION:
LITTLE LLANO 055 25.0
END DESCRIPTION:
XS GIS Cut Line= 3
      2836055.71     10285953.13      2835835.50     10285822.00
      2835555.66     10285753.10
#Sta/Elev= 30
  4743.7 1249.55  4746.6 1249.55  4767.0 1244.69  4772.9 1242.40  4817.9 1230.14
  4825.2 1227.50  4831.4 1222.98  4837.2 1221.62  4847.0 1217.04  4852.8 1215.90
  4860.1 1212.27  4889.8 1203.35  4895.6 1201.88  4911.2 1199.83  4963.8 1194.84
  4969.6 1192.90  4976.5 1189.05  4983.2 1187.14  4983.4 1186.64  4986.9 1186.64
  4987.2 1187.14  5002.5 1187.93  5020.9 1190.28  5057.3 1193.25  5098.8 1195.21
  5123.4 1195.32  5188.6 1200.04  5236.7 1205.46  5257.3 1206.65  5288.2 1210.95
#Mann=5,-1,0
  4743.7    0.12       0  4817.9    0.05       0  4983.2    0.03       0
  4987.2    0.05       0  5188.6    0.12       0
Bank Sta=4983.2,4987.2
Exp/Cntr=0.3,0.1

Type RM Length L Ch R = 1,12884,461,461,461
BEGIN DESCRIPTION:
LITTLE LLANO 055 24.0
END DESCRIPTION:
XS GIS Cut Line= 3
      2836105.71     10285503.13      2835904.75     10285371.00
      2835605.72     10285453.10
#Sta/Elev= 30
  4759.5 1223.41  4762.5 1223.41  4767.1 1220.69  4788.1 1217.50  4803.2 1212.09
  4809.2 1211.62  4818.3 1208.97  4824.3 1209.13  4839.4 1205.28  4896.6 1197.55
  4917.7 1192.99  4926.7 1189.95  4932.8 1189.24  4947.8 1184.01  4953.8 1184.17
  4962.9 1181.09  4972.7 1180.11  4972.9 1180.08  4973.2 1179.58  4976.9 1180.08
  5002.1 1182.12  5025.9 1186.05  5040.5 1187.20  5100.0 1186.09  5203.6 1190.40
  5227.2 1192.95  5253.3 1197.93  5258.5 1197.72  5307.3 1203.51  5310.1 1203.53
#Mann=9,-1,0
  4759.5    0.12       0  4788.1    0.05       0  4926.7    0.12       0
  4972.7    0.05       0  4972.9    0.05       0  4976.9    0.05       0
  5100.0    0.12       0  5203.6    0.05       0  5307.3    0.12       0
Bank Sta=4972.9,4976.9
Exp/Cntr=0.3,0.1

Type RM Length L Ch R = 1,12423,463,463,463
BEGIN DESCRIPTION:
LITTLE LLANO 055 23.0
END DESCRIPTION:
XS GIS Cut Line= 3
      2835905.72     10285003.10      2835627.00     10285069.00
      2835555.65     10285053.10
#Sta/Elev= 30
  4713.6 1201.22  4723.9 1200.57  4754.7 1196.37  4765.0 1193.51  4774.5 1189.95
  4779.6 1190.15  4785.6 1187.00  4795.8 1186.03  4806.1 1183.53  4821.9 1180.78
  4857.5 1180.33  4869.3 1179.54  4911.6 1180.11  4948.8 1179.34  4953.9 1180.17
  4991.0 1176.52  4996.2 1177.92  5002.0 1177.49  5005.3 1175.25  5011.6 1174.05
  5030.1 1172.17  5030.3 1171.67  5033.8 1171.67  5034.1 1172.17  5042.3 1173.16
  5048.8 1176.29  5053.9 1180.02  5062.8 1184.13  5070.5 1186.02  5073.1 1186.02
#Mann=3,-1,0
  4713.6    0.05       0  5030.1    0.05       0  5034.1    0.05       0
Bank Sta=5030.1,5034.1
Exp/Cntr=0.3,0.1

Type RM Length L Ch R = 1,11960,466,466,466
BEGIN DESCRIPTION:
LITTLE LLANO 055 22.0
END DESCRIPTION:
XS GIS Cut Line= 3
      2835905.69     10284803.12      2835821.50     10284656.00
      2835655.72     10284503.14
#Sta/Elev= 30
  4830.5 1189.14  4833.4 1189.14  4838.4 1187.32  4844.2 1187.27  4860.0 1183.47
  4881.6 1181.10  4897.4 1178.22  4922.7 1175.42  4956.4 1171.89  4968.8 1168.49
  4996.8 1164.36  4997.0 1163.86  5000.5 1163.86  5000.8 1164.36  5013.2 1164.60
  5027.4 1167.37  5034.7 1169.53  5048.7 1171.17  5098.2 1175.04  5105.0 1178.44
  5112.4 1180.24  5119.2 1184.24  5126.6 1186.31  5133.4 1189.62  5140.8 1191.33
  5154.9 1196.54  5190.1 1206.18  5197.5 1208.85  5222.1 1215.00  5225.5 1215.00
#Mann=4,-1,0
  4830.5    0.05       0  4922.7    0.12       0  4996.8    0.07       0
  5000.8    0.12       0
Bank Sta=4996.8,5000.8
Exp/Cntr=0.3,0.1

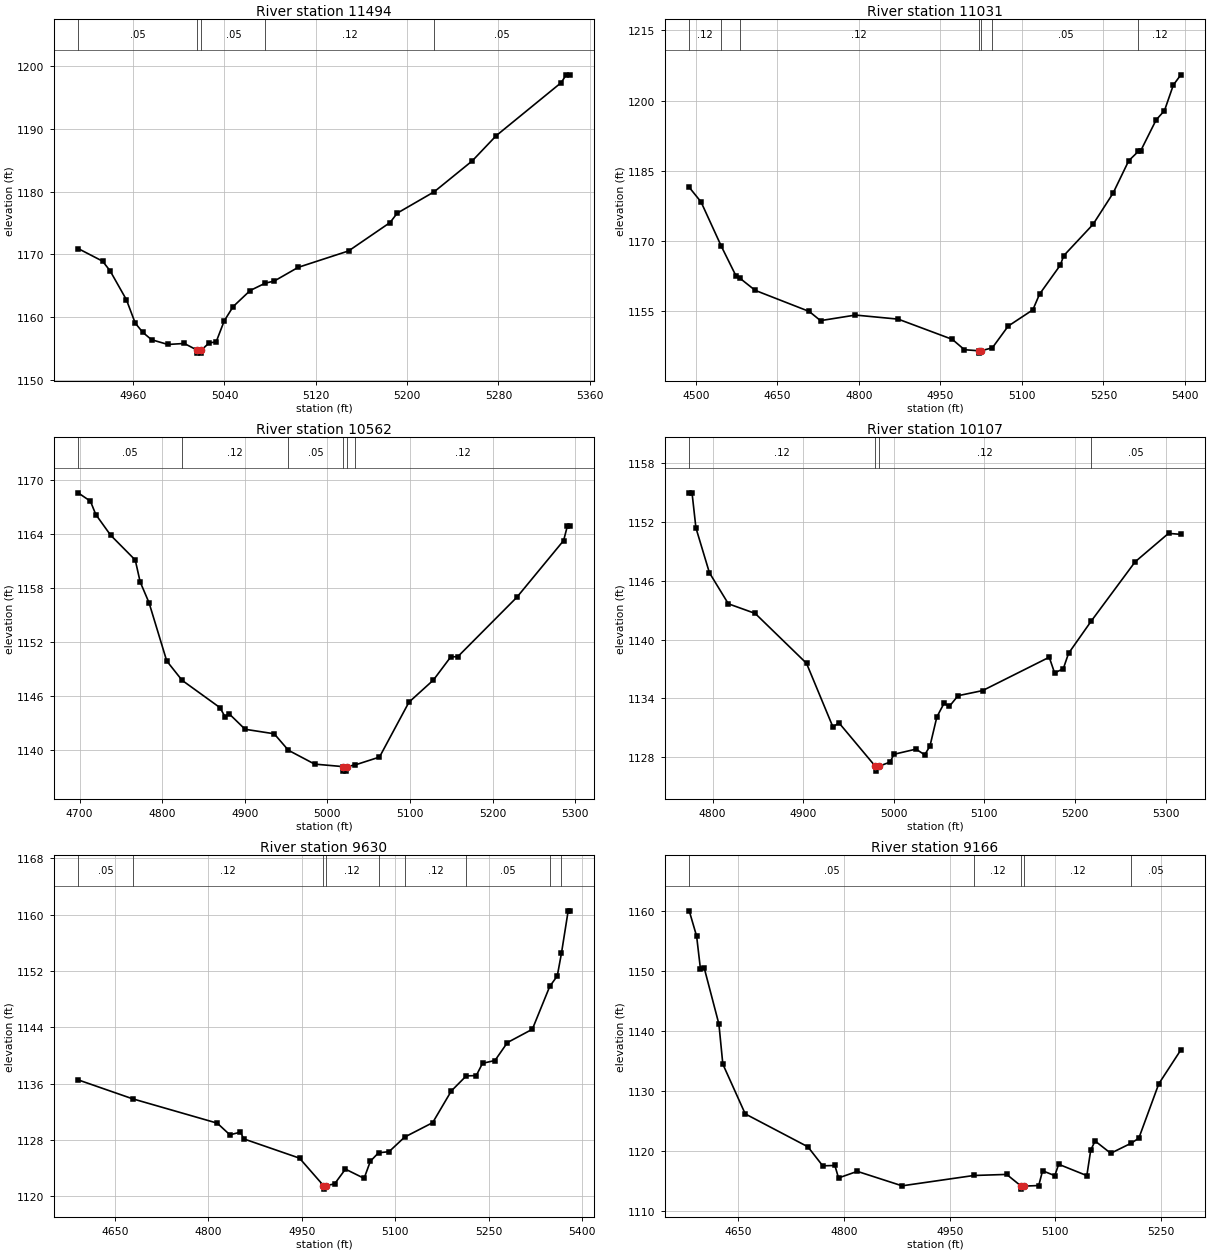
Type RM Length L Ch R = 1,11494,463,463,463
BEGIN DESCRIPTION:
LITTLE LLANO 055 21.0
END DESCRIPTION:
XS GIS Cut Line= 3
      2836305.70     10284553.13      2836248.50     10284486.00
      2836055.66     10284203.07
#Sta/Elev= 30
  4911.8 1170.93  4933.2 1168.92  4939.8 1167.38  4954.1 1162.77  4961.8 1159.05
  4968.4 1157.58  4976.1 1156.40  4990.4 1155.64  5004.8 1155.80  5015.8 1154.76
  5016.0 1154.26  5019.5 1154.26  5019.8 1154.76  5026.6 1155.89  5032.7 1156.05
  5039.8 1159.41  5047.6 1161.68  5062.5 1164.24  5075.8 1165.42  5083.5 1165.74
  5104.5 1167.93  5148.7 1170.55  5185.0 1175.07  5191.3 1176.57  5223.7 1179.98
  5257.0 1184.90  5278.0 1188.92  5334.9 1197.37  5339.3 1198.62  5342.4 1198.62
#Mann=5,-1,0
  4911.8    0.05       0  5015.8    0.05       0  5019.8    0.05       0
  5075.8    0.12       0  5223.7    0.05       0
Bank Sta=5015.8,5019.8
Exp/Cntr=0.3,0.1

Type RM Length L Ch R = 1,11031,469,469,469
BEGIN DESCRIPTION:
LITTLE LLANO 055 20.0
END DESCRIPTION:
XS GIS Cut Line= 3
      2836955.69     10284653.12      2836641.00     10284249.00
      2836455.69     10283903.11
#Sta/Elev= 30
  4487.8 1181.49  4509.5 1178.38  4547.0 1168.87  4573.8 1162.59  4580.6 1162.12
  4609.1 1159.49  4708.6 1154.98  4729.4 1153.02  4793.6 1154.21  4872.3 1153.34
  4971.9 1149.02  4994.2 1146.81  5020.7 1146.58  5021.0 1146.08  5024.8 1146.58
  5045.6 1147.22  5074.7 1151.85  5120.1 1155.33  5132.4 1158.67  5170.6 1164.87
  5176.9 1166.89  5230.7 1173.56  5267.6 1180.22  5296.5 1187.17  5314.2 1189.17
  5318.5 1189.28  5347.0 1195.90  5362.3 1197.88  5378.6 1203.34  5392.4 1205.52
#Mann=7,-1,0
  4487.8    0.12       0  4547.0    0.05       0  4580.6    0.12       0
  5020.7    0.07       0  5024.8    0.12       0  5045.6    0.05       0
  5314.2    0.12       0
Bank Sta=5020.7,5024.8
Exp/Cntr=0.3,0.1

Type RM Length L Ch R = 1,10562,455,455,455
BEGIN DESCRIPTION:
LITTLE LLANO 055 19.0
END DESCRIPTION:
XS GIS Cut Line= 3
      2837205.67     10284503.07      2837095.75     10284222.00
      2836855.70     10284053.12
#Sta/Elev= 30
  4698.2 1168.54  4713.1 1167.61  4719.6 1166.13  4737.5 1163.84  4767.4 1161.07
  4773.3 1158.65  4784.1 1156.32  4805.5 1149.86  4824.1 1147.71  4870.0 1144.67
  4876.0 1143.67  4881.3 1143.97  4900.4 1142.27  4935.6 1141.77  4952.8 1139.94
  4984.6 1138.40  5019.2 1138.12  5019.5 1137.62  5023.1 1137.62  5023.3 1138.12
  5033.7 1138.31  5063.1 1139.18  5098.8 1145.28  5128.4 1147.74  5149.4 1150.31
  5158.0 1150.34  5229.5 1156.94  5286.1 1163.24  5290.5 1164.80  5293.5 1164.80
#Mann=6,-1,0
  4698.2    0.05       0  4824.1    0.12       0  4952.8    0.05       0
  5019.2    0.03       0  5023.3    0.05       0  5033.7    0.12       0
Bank Sta=5019.2,5023.3
Exp/Cntr=0.3,0.1

Type RM Length L Ch R = 1,10107,477,477,477
BEGIN DESCRIPTION:
LITTLE LLANO 055 18.0
END DESCRIPTION:
XS GIS Cut Line= 3
      2837505.70     10284103.13      2837376.25     10283918.00
      2837105.64     10283753.09
#Sta/Elev= 30
  4774.1 1154.94  4777.2 1154.94  4781.5 1151.37  4796.4 1146.80  4817.3 1143.64
  4846.9 1142.66  4903.6 1137.58  4932.8 1131.09  4939.4 1131.52  4979.5 1127.10
  4979.8 1126.60  4983.7 1127.10  4996.1 1127.53  4999.9 1128.31  5024.5 1128.84
  5034.1 1128.26  5039.9 1129.15  5047.5 1132.11  5055.4 1133.50  5061.3 1133.19
  5070.9 1134.28  5098.0 1134.80  5171.6 1138.20  5177.5 1136.60  5187.1 1137.02
  5192.9 1138.59  5217.9 1141.87  5266.5 1147.92  5303.3 1150.81  5316.9 1150.71
#Mann=4,-1,0
  4774.1    0.12       0  4979.5    0.07       0  4983.7    0.12       0
  5217.9    0.05       0
Bank Sta=4979.5,4983.7
Exp/Cntr=0.3,0.1

Type RM Length L Ch R = 1,9630,464,464,464
BEGIN DESCRIPTION:
LITTLE LLANO 055 17.0
END DESCRIPTION:
XS GIS Cut Line= 3
      2837655.69     10283903.14      2837585.50     10283500.00
      2837205.71     10283503.11
#Sta/Elev= 30
  4590.8 1136.52  4678.2 1133.83  4814.1 1130.37  4834.4 1128.71  4851.4 1129.10
  4856.5 1128.14  4946.1 1125.40  4984.6 1121.50  4984.8 1121.00  4988.8 1121.50
  5002.4 1121.74  5019.8 1123.84  5049.8 1122.53  5059.8 1124.96  5072.9 1126.16
  5089.8 1126.32  5114.8 1128.39  5159.8 1130.44  5189.8 1134.95  5213.7 1137.08
  5229.8 1137.13  5239.8 1138.87  5259.8 1139.27  5279.8 1141.82  5319.8 1143.71
  5347.7 1149.79  5359.8 1151.28  5366.5 1154.50  5377.3 1160.53  5379.8 1160.53
#Mann=9,-1,0
  4590.8    0.05       0  4678.2    0.12       0  4984.6    0.07       0
  4988.8    0.12       0  5072.9    0.05       0  5114.8    0.12       0
  5213.7    0.05       0  5347.7    0.12       0  5366.5    0.05       0
Bank Sta=4984.6,4988.8
Exp/Cntr=0.3,0.1

Type RM Length L Ch R = 1,9166,466,466,466
BEGIN DESCRIPTION:
LITTLE LLANO 055 16.0
END DESCRIPTION:
XS GIS Cut Line= 3
      2838355.69     10283453.11      2837957.00     10283322.00
      2837705.70     10283203.12
#Sta/Elev= 30
  4580.3 1159.99  4590.8 1155.77  4596.2 1150.34  4601.5 1150.51  4622.4 1141.14
  4628.0 1134.46  4659.8 1126.17  4748.7 1120.69  4769.8 1117.52  4787.0 1117.58
  4792.2 1115.50  4818.8 1116.60  4882.4 1114.19  4984.1 1115.91  5030.8 1116.09
  5051.4 1114.14  5051.7 1113.64  5055.7 1114.14  5076.3 1114.24  5081.8 1116.70
  5099.1 1115.88  5104.6 1117.78  5144.6 1115.89  5150.1 1120.12  5156.3 1121.66
  5178.5 1119.61  5207.7 1121.30  5218.4 1122.13  5246.7 1131.18  5278.0 1136.82
#Mann=5,-1,0
  4580.3    0.05       0  4984.1    0.12       0  5051.4    0.07       0
  5055.7    0.12       0  5207.7    0.05       0
Bank Sta=5051.4,5055.7
Exp/Cntr=0.3,0.1

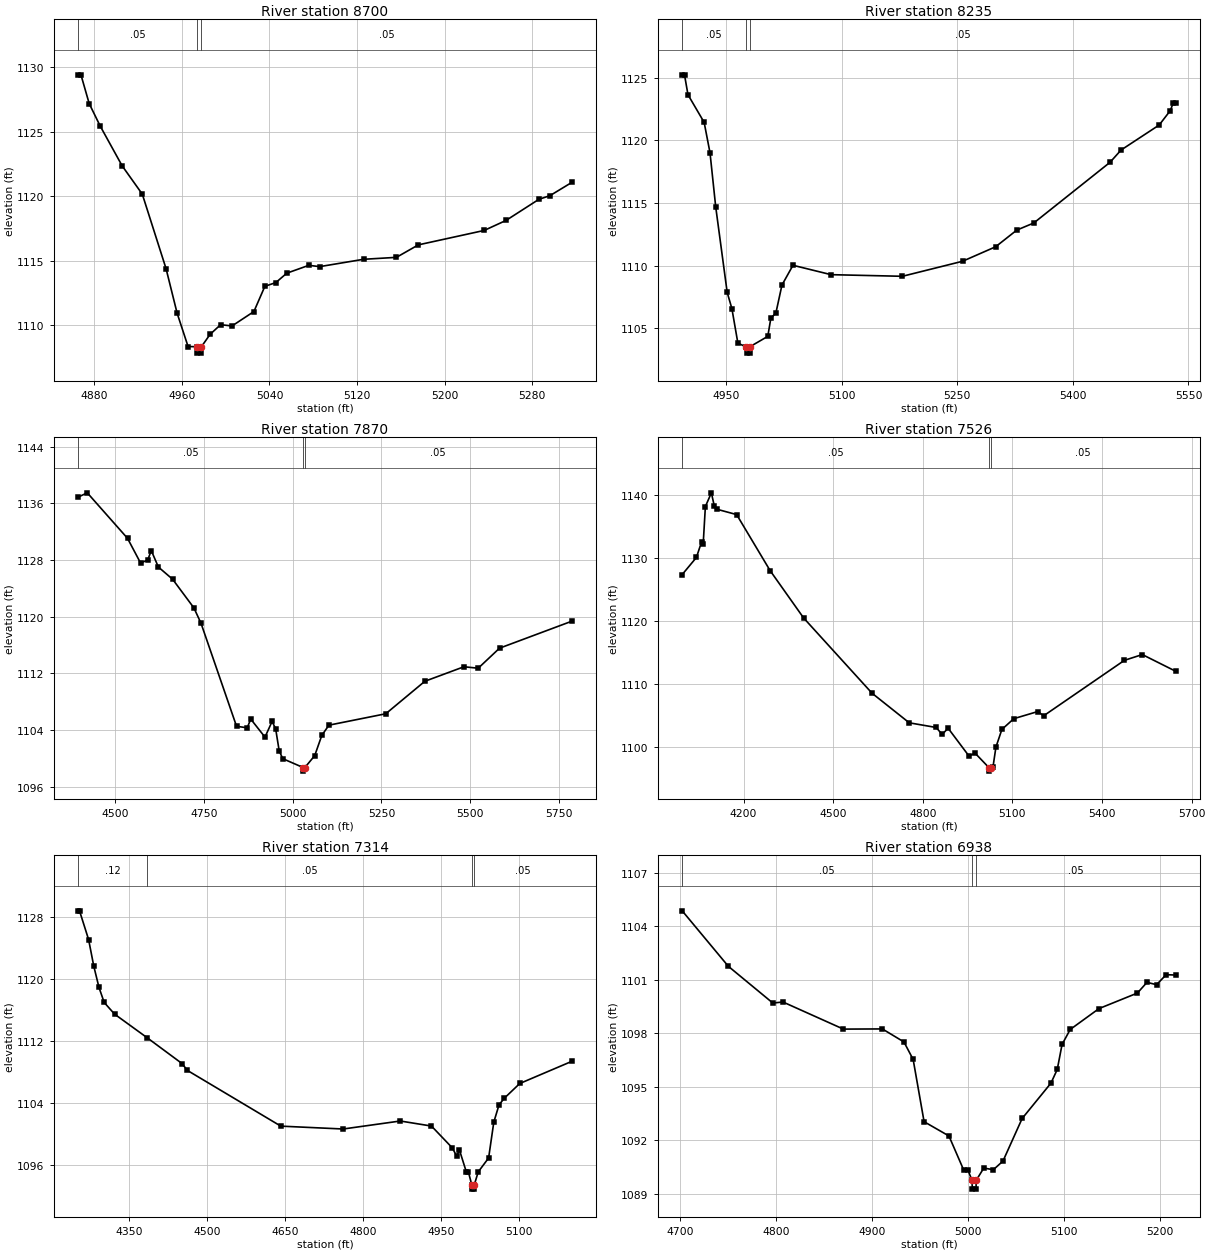
Type RM Length L Ch R = 1,8700,465,465,465
BEGIN DESCRIPTION:
LITTLE LLANO 055 15.0
END DESCRIPTION:
XS GIS Cut Line= 3
      2838455.66     10283103.11      2838321.50     10283114.00
      2838005.69     10283103.11
#Sta/Elev= 30
  4865.4 1129.43  4867.9 1129.43  4875.4 1127.20  4885.4 1125.46  4905.5 1122.36
  4923.9 1120.16  4945.6 1114.37  4955.7 1110.91  4965.7 1108.32  4973.6 1108.31
  4973.9 1107.81  4977.6 1107.81  4977.9 1108.31  4985.8 1109.27  4995.4 1110.02
  5005.8 1109.92  5025.8 1111.04  5035.8 1113.00  5045.8 1113.29  5055.8 1114.02
  5075.9 1114.63  5085.9 1114.53  5125.9 1115.10  5155.9 1115.25  5175.9 1116.22
  5236.0 1117.34  5256.0 1118.12  5286.0 1119.76  5296.0 1120.04  5316.0 1121.07
#Mann=3,-1,0
  4865.4    0.05       0  4973.6    0.03       0  4977.9    0.05       0
Bank Sta=4973.6,4977.9
Exp/Cntr=0.3,0.1

Type RM Length L Ch R = 1,8235,365,365,365
BEGIN DESCRIPTION:
LITTLE LLANO 055 14.0
END DESCRIPTION:
XS GIS Cut Line= 3
      2838455.67     10282603.12      2838366.75     10282663.00
      2837955.70     10283003.09
#Sta/Elev= 30
  4892.8 1125.24  4895.8 1125.24  4900.3 1123.65  4921.3 1121.44  4928.9 1119.01
  4936.3 1114.69  4951.2 1107.85  4957.3 1106.56  4965.1 1103.79  4976.1 1103.50
  4976.4 1103.00  4980.2 1103.00  4980.4 1103.50  5003.9 1104.34  5007.9 1105.80
  5014.4 1106.20  5022.3 1108.44  5036.6 1110.02  5086.1 1109.27  5178.6 1109.14
  5256.7 1110.34  5299.7 1111.50  5327.1 1112.83  5349.2 1113.40  5448.2 1118.25
  5462.5 1119.23  5512.0 1121.23  5526.4 1122.38  5530.3 1123.01  5533.5 1123.01
#Mann=3,-1,0
  4892.8    0.05       0  4976.1    0.03       0  4980.4    0.05       0
Bank Sta=4976.1,4980.4
Exp/Cntr=0.3,0.1

Type RM Length L Ch R = 1,7870,344,344,344
BEGIN DESCRIPTION:
Mapping XS f7f731b3
END DESCRIPTION:
XS GIS Cut Line= 2
      2838691.21     10282435.97      2837302.28     10282457.68
#Sta/Elev= 30
  4396.5 1136.88  4422.0 1137.48  4535.2 1131.06  4572.0 1127.57  4592.1 1127.99
  4602.1 1129.33  4622.1 1127.00  4662.1 1125.28  4722.1 1121.23  4742.1 1119.06
  4842.1 1104.51  4872.1 1104.30  4882.1 1105.53  4922.1 1102.98  4942.1 1105.19
  4952.1 1104.17  4962.1 1101.05  4972.1 1099.94  5029.9 1098.68  5030.2 1098.18
  5034.3 1098.68  5062.1 1100.37  5082.1 1103.23  5102.1 1104.67  5262.1 1106.28
  5372.1 1110.87  5482.2 1112.92  5522.2 1112.71  5582.2 1115.54  5785.6 1119.35
#Mann=3,-1,0
  4396.5    0.05       0  5029.9    0.03       0  5034.3    0.05       0
Bank Sta=5029.9,5034.3
Exp/Cntr=0.3,0.1

Type RM Length L Ch R = 1,7526,212,212,212
BEGIN DESCRIPTION:
Mapping XS 8354c11f
END DESCRIPTION:
XS GIS Cut Line= 3
      2838843.03     10282284.06      2838105.23     10282218.96
      2837193.76     10282197.26
#Sta/Elev= 30
  3994.4 1127.38  4041.9 1130.09  4059.5 1132.60  4064.6 1132.18  4072.0 1138.19
  4092.1 1140.37  4102.2 1138.20  4112.2 1137.74  4176.7 1136.91  4288.8 1128.00
  4400.9 1120.48  4630.1 1108.51  4754.6 1103.81  4844.6 1103.07  4864.7 1101.97
  4884.7 1102.95  4954.7 1098.52  4974.7 1099.00  5022.5 1096.63  5022.8 1096.13
  5026.9 1096.63  5034.7 1096.72  5044.7 1099.94  5064.7 1102.76  5104.7 1104.47
  5184.7 1105.60  5204.7 1104.93  5474.8 1113.74  5534.8 1114.66  5646.8 1112.00
#Mann=3,-1,0
  3994.4    0.05       0  5022.5    0.03       0  5026.9    0.05       0
Bank Sta=5022.5,5026.9
Exp/Cntr=0.3,0.1

Type RM Length L Ch R = 1,7314,376,376,376
BEGIN DESCRIPTION:
LITTLE LLANO 055 12.0
END DESCRIPTION:
XS GIS Cut Line= 3
      2838455.68     10282053.11      2837707.00     10282048.00
      2837505.66     10282053.11
#Sta/Elev= 30
  4251.3 1128.74  4253.8 1128.74  4271.3 1125.04  4281.3 1121.60  4291.3 1118.87
  4301.3 1116.94  4321.3 1115.44  4383.6 1112.42  4451.3 1109.07  4461.3 1108.20
  4641.3 1101.02  4761.3 1100.65  4871.3 1101.68  4931.3 1101.03  4971.3 1098.23
  4980.0 1097.14  4985.0 1097.98  4998.2 1095.17  5002.2 1095.17  5009.1 1093.41
  5009.4 1092.91  5013.2 1092.91  5013.5 1093.41  5021.3 1095.13  5041.3 1096.92
  5051.3 1101.54  5061.3 1103.75  5071.3 1104.60  5101.3 1106.51  5201.4 1109.36
#Mann=4,-1,0
  4251.3    0.12       0  4383.6    0.05       0  5009.1    0.03       0
  5013.5    0.05       0
Bank Sta=5009.1,5013.5
Exp/Cntr=0.3,0.1

Type RM Length L Ch R = 1,6938,923,923,923
BEGIN DESCRIPTION:
LITTLE LLANO 055 11.0
END DESCRIPTION:
XS GIS Cut Line= 3
      2838205.67     10281903.11      2837922.25     10281812.00
      2837705.73     10281803.11
#Sta/Elev= 30
  4702.3 1104.86  4750.4 1101.75  4796.8 1099.69  4807.3 1099.75  4870.3 1098.23
  4910.9 1098.24  4933.4 1097.51  4943.0 1096.53  4954.4 1093.04  4980.3 1092.24
  4995.6 1090.34  5000.0 1090.34  5004.3 1089.76  5004.7 1089.26  5008.5 1089.26
  5008.8 1089.76  5016.6 1090.44  5026.6 1090.35  5036.6 1090.83  5056.6 1093.22
  5086.6 1095.20  5093.2 1095.97  5098.2 1097.37  5106.7 1098.21  5136.7 1099.38
  5176.7 1100.25  5186.7 1100.85  5196.7 1100.72  5206.7 1101.28  5216.7 1101.26
#Mann=3,-1,0
  4702.3    0.05       0  5004.3    0.03       0  5008.8    0.05       0
Bank Sta=5004.3,5008.8
Exp/Cntr=0.3,0.1