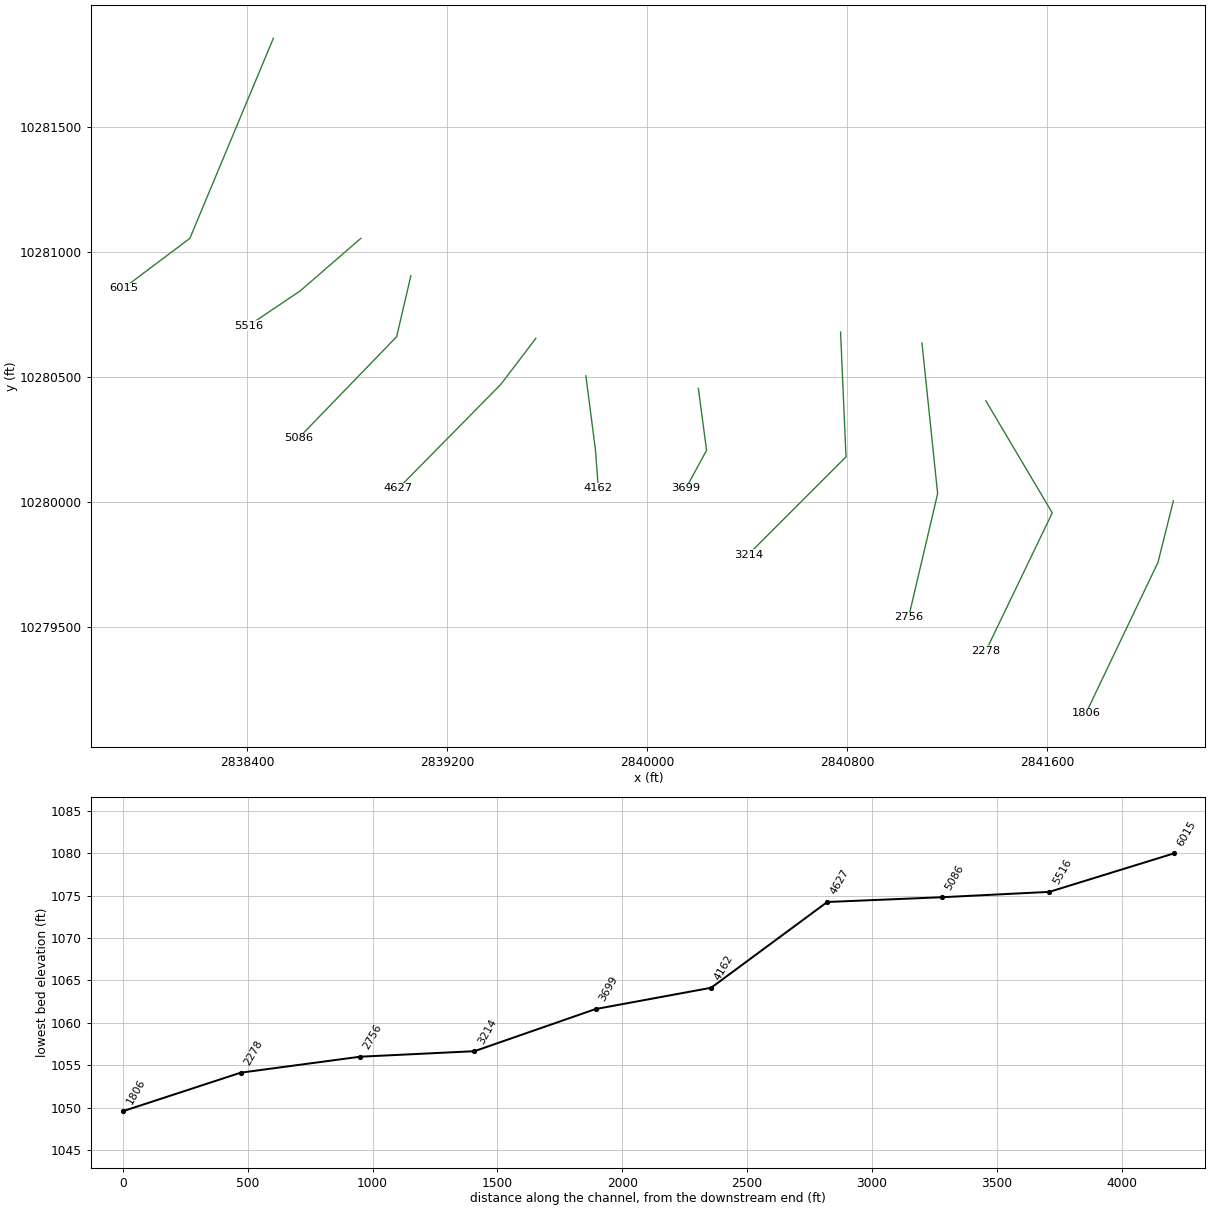
HEC-RAS study LITTLE LLANO 055.prj: LITTLE LLANO 055 Base Level Engineering

--- LITTLE LLANO 055.g01 (geometry) --- (continued)

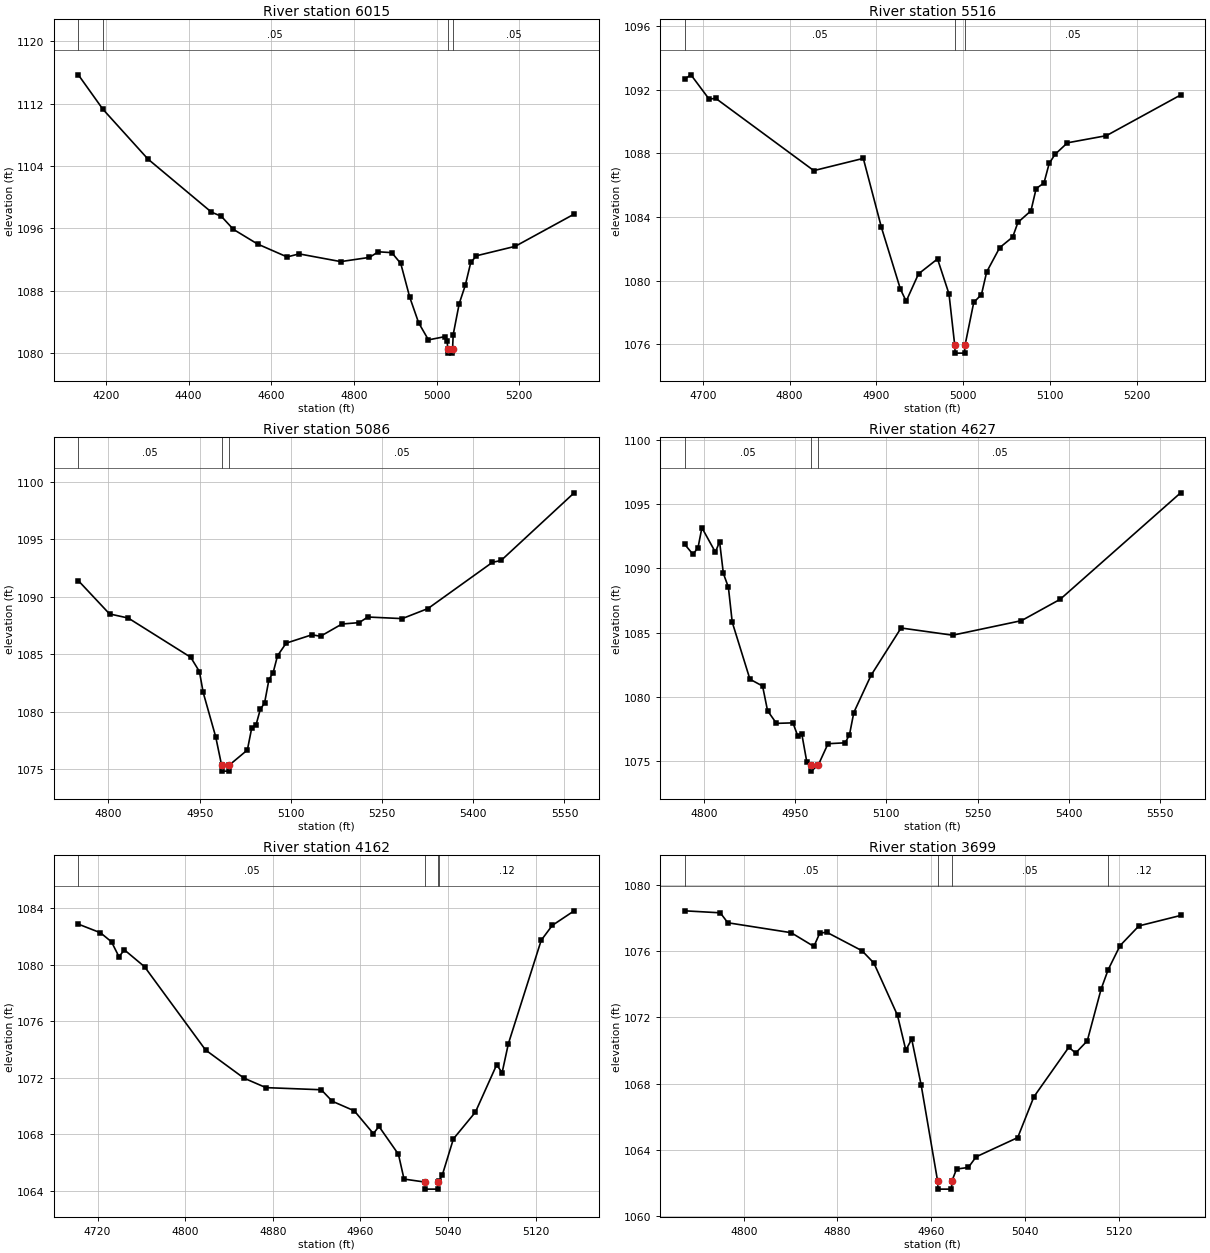
Type RM Length L Ch R = 1,6015,499,499,499
BEGIN DESCRIPTION:
LITTLE LLANO 055 10.0
END DESCRIPTION:
XS GIS Cut Line= 3
      2838505.68     10281853.11      2838171.75     10281053.00
      2837905.67     10280853.10
#Sta/Elev= 30
  4133.0 1115.69  4192.3 1111.28  4301.4 1104.88  4455.1 1098.06  4478.9 1097.53
  4508.2 1095.85  4566.6 1093.97  4638.1 1092.31  4667.3 1092.70  4768.0 1091.71
  4837.3 1092.25  4859.0 1092.97  4891.5 1092.86  4913.2 1091.47  4934.9 1087.14
  4956.5 1083.85  4980.2 1081.66  5019.3 1082.07  5025.6 1081.57  5026.7 1080.46
  5027.2 1079.96  5038.0 1079.96  5038.5 1080.46  5040.1 1082.34  5054.7 1086.32
  5069.3 1088.66  5082.6 1091.60  5096.4 1092.46  5190.1 1093.67  5332.8 1097.81
#Mann=4,-1,0
  4133.0    0.12       0  4192.3    0.05       0  5026.7    0.05       0
  5038.5    0.05       0
Bank Sta=5026.7,5038.5
Exp/Cntr=0.3,0.1

Type RM Length L Ch R = 1,5516,430,430,430
BEGIN DESCRIPTION:
LITTLE LLANO 055 9.0
END DESCRIPTION:
XS GIS Cut Line= 3
      2838855.67     10281053.10      2838613.25     10280843.00
      2838405.69     10280703.11
#Sta/Elev= 30
  4679.2 1092.69  4686.3 1092.95  4707.2 1091.42  4714.8 1091.47  4827.8 1086.92
  4884.8 1087.69  4905.7 1083.34  4927.6 1079.45  4934.2 1078.70  4948.4 1080.42
  4970.3 1081.36  4983.5 1079.16  4990.1 1075.93  4990.6 1075.43  5001.5 1075.43
  5002.0 1075.93  5012.0 1078.62  5020.9 1079.12  5026.9 1080.54  5041.9 1082.07
  5056.9 1082.74  5062.9 1083.66  5077.9 1084.39  5083.9 1085.79  5092.9 1086.14
  5098.9 1087.37  5105.6 1087.94  5119.9 1088.67  5164.8 1089.12  5250.3 1091.68
#Mann=3,-1,0
  4679.2    0.05       0  4990.1    0.03       0  5002.0    0.05       0
Bank Sta=4990.1,5002
Exp/Cntr=0.3,0.1

Type RM Length L Ch R = 1,5086,459,459,459
BEGIN DESCRIPTION:
LITTLE LLANO 055 8.0
END DESCRIPTION:
XS GIS Cut Line= 3
      2839055.68     10280903.08      2838999.00     10280660.00
      2838605.69     10280253.12
#Sta/Elev= 30
  4750.4 1091.41  4801.7 1088.51  4832.5 1088.15  4935.2 1084.73  4949.6 1083.48
  4955.7 1081.67  4976.3 1077.80  4986.1 1075.30  4986.6 1074.80  4997.6 1074.80
  4998.1 1075.30  5028.4 1076.64  5035.6 1078.57  5042.5 1078.80  5049.7 1080.19
  5056.7 1080.74  5063.9 1082.78  5070.8 1083.39  5078.0 1084.86  5092.2 1085.96
  5134.6 1086.69  5148.7 1086.56  5184.0 1087.63  5212.3 1087.75  5226.5 1088.24
  5283.1 1088.10  5325.5 1088.98  5431.5 1093.01  5445.7 1093.17  5565.9 1099.07
#Mann=3,-1,0
  4750.4    0.05       0  4986.1    0.05       0  4998.1    0.05       0
Bank Sta=4986.1,4998.1
Exp/Cntr=0.3,0.1

Type RM Length L Ch R = 1,4627,465,465,465
BEGIN DESCRIPTION:
LITTLE LLANO 055 7.0
END DESCRIPTION:
XS GIS Cut Line= 3
      2839555.68     10280653.11      2839415.50     10280469.00
      2839005.67     10280053.10
#Sta/Elev= 30
  4768.6 1091.85  4782.1 1091.08  4790.4 1091.61  4796.7 1093.15  4818.9 1091.25
  4825.8 1092.07  4832.0 1089.60  4840.3 1088.52  4846.6 1085.81  4875.7 1081.38
  4896.5 1080.85  4904.7 1078.93  4919.3 1077.95  4946.4 1077.99  4954.6 1076.94
  4960.9 1077.15  4969.2 1074.96  4976.3 1074.74  4976.8 1074.24  4988.3 1074.74
  5004.1 1076.37  5032.3 1076.44  5039.4 1077.07  5046.5 1078.79  5074.8 1081.68
  5124.2 1085.36  5209.1 1084.80  5322.2 1085.93  5385.9 1087.59  5583.9 1095.86
#Mann=3,-1,0
  4768.6    0.05       0  4976.3    0.05       0  4988.3    0.05       0
Bank Sta=4976.3,4988.3
Exp/Cntr=0.3,0.1

Type RM Length L Ch R = 1,4162,463,463,463
BEGIN DESCRIPTION:
LITTLE LLANO 055 6.0
END DESCRIPTION:
XS GIS Cut Line= 3
      2839755.68     10280503.12      2839794.00     10280208.00
      2839805.68     10280053.14
#Sta/Elev= 30
  4702.4 1082.86  4722.6 1082.25  4732.7 1081.61  4739.5 1080.56  4744.5 1081.04
  4762.9 1079.85  4818.6 1073.97  4853.7 1071.98  4873.8 1071.31  4924.3 1071.16
  4934.3 1070.35  4954.5 1069.67  4971.9 1068.06  4977.0 1068.57  4994.8 1066.60
  4999.9 1064.85  5018.9 1064.64  5019.4 1064.14  5030.6 1064.14  5031.1 1064.64
  5031.5 1064.69  5035.0 1065.17  5045.0 1067.69  5065.1 1069.58  5084.5 1072.92
  5089.5 1072.37  5095.2 1074.41  5125.2 1081.72  5135.3 1082.77  5155.3 1083.80
#Mann=4,-1,0
  4702.4    0.05       0  5018.9    0.05       0  5031.1    0.05       0
  5031.5    0.12       0
Bank Sta=5018.9,5031.1
Exp/Cntr=0.3,0.1

Type RM Length L Ch R = 1,3699,485,485,485
BEGIN DESCRIPTION:
LITTLE LLANO 055 5.0
END DESCRIPTION:
XS GIS Cut Line= 3
      2840205.68     10280453.14      2840238.50     10280205.00
      2840155.68     10280053.11
#Sta/Elev= 30
  4749.7 1078.43  4780.0 1078.31  4786.4 1077.71  4840.5 1077.11  4859.9 1076.28
  4864.9 1077.08  4870.8 1077.14  4901.0 1076.02  4911.1 1075.28  4931.3 1072.12
  4938.4 1070.02  4943.4 1070.69  4951.5 1067.91  4965.5 1062.13  4966.0 1061.63
  4977.3 1061.63  4977.8 1062.13  4981.7 1062.84  4991.8 1062.94  4998.4 1063.58
  5033.9 1064.74  5047.7 1067.20  5077.6 1070.20  5083.3 1069.84  5093.3 1070.58
  5105.1 1073.70  5111.1 1074.87  5121.3 1076.33  5137.4 1077.52  5173.0 1078.15
#Mann=4,-1,0
  4749.7    0.05       0  4965.5    0.05       0  4977.8    0.05       0
  5111.1    0.12       0
Bank Sta=4965.5,4977.8
Exp/Cntr=0.3,0.1

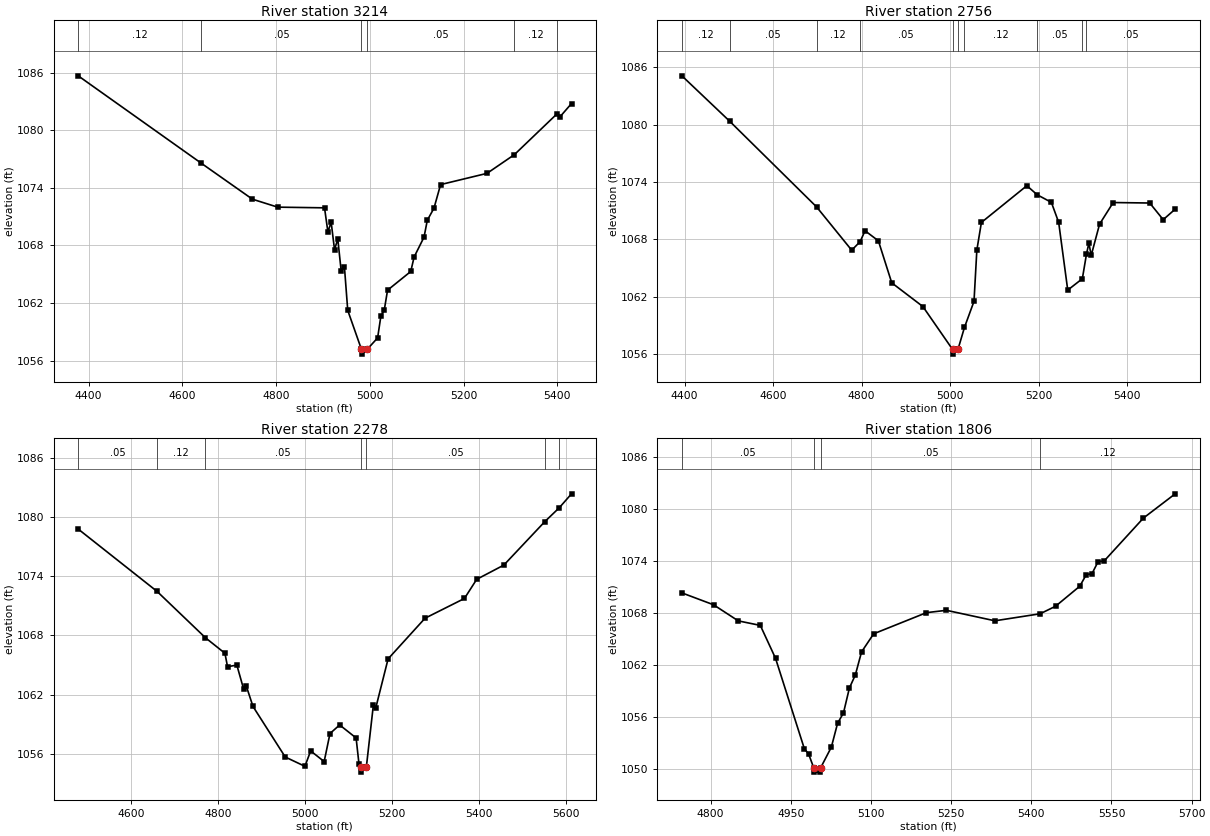
Type RM Length L Ch R = 1,3214,458,458,458
BEGIN DESCRIPTION:
Mapping XS 97416e4a
END DESCRIPTION:
XS GIS Cut Line= 3
      2840774.50     10280678.14      2840796.20     10280179.03
      2840405.58     10279788.41
#Sta/Elev= 30
  4378.0 1085.66  4640.9 1076.54  4749.5 1072.81  4803.4 1071.98  4903.3 1071.91
  4910.4 1069.43  4917.5 1070.39  4924.6 1067.56  4931.6 1068.66  4938.7 1065.38
  4945.8 1065.73  4952.8 1061.23  4982.0 1057.17  4982.5 1056.67  4994.3 1057.17
  5016.5 1058.36  5023.6 1060.67  5030.6 1061.23  5037.7 1063.33  5087.2 1065.28
  5094.3 1066.78  5115.5 1068.86  5122.5 1070.62  5136.7 1071.87  5150.8 1074.33
  5249.8 1075.50  5308.2 1077.45  5398.4 1081.67  5405.4 1081.39  5430.0 1082.77
#Mann=6,-1,0
  4378.0    0.12       0  4640.9    0.05       0  4982.0    0.05       0
  4994.3    0.05       0  5308.2    0.12       0  5398.4    0.05       0
Bank Sta=4982,4994.3
Exp/Cntr=0.3,0.1

Type RM Length L Ch R = 1,2756,478,478,478
BEGIN DESCRIPTION:
LITTLE LLANO 055 3.0
END DESCRIPTION:
XS GIS Cut Line= 3
      2841100.02     10280634.74      2841162.75     10280032.00
      2841046.48     10279536.77
#Sta/Elev= 30
  4394.0 1085.10  4501.7 1080.37  4698.4 1071.40  4777.7 1066.88  4796.7 1067.77
  4807.9 1068.91  4838.0 1067.86  4868.2 1063.47  4938.6 1060.99  5005.5 1056.52
  5006.0 1056.02  5017.9 1056.52  5032.5 1058.81  5054.1 1061.54  5060.5 1066.89
  5070.8 1069.78  5173.5 1073.62  5196.9 1072.67  5228.9 1071.88  5245.4 1069.79
  5265.9 1062.71  5298.9 1063.90  5308.2 1066.46  5313.7 1067.63  5318.9 1066.33
  5337.8 1069.60  5368.6 1071.86  5451.2 1071.81  5481.6 1070.07  5508.7 1071.17
#Mann=10,-1,0
  4394.0    0.12       0  4501.7    0.05       0  4698.4    0.12       0
  4796.7    0.05       0  5005.5    0.03       0  5017.9    0.05       0
  5032.5    0.12       0  5196.9    0.05       0  5298.9    0.12       0
  5308.2    0.05       0
Bank Sta=5005.5,5017.9
Exp/Cntr=0.3,0.1

Type RM Length L Ch R = 1,2278,472,472,472
BEGIN DESCRIPTION:
LITTLE LLANO 055 2.0
END DESCRIPTION:
XS GIS Cut Line= 3
      2841355.68     10280403.12      2841621.25     10279955.00
      2841355.67     10279403.07
#Sta/Elev= 30
  4479.1 1078.76  4660.2 1072.45  4771.5 1067.75  4816.2 1066.18  4822.2 1064.82
  4843.6 1064.98  4859.2 1062.55  4865.1 1062.88  4880.7 1060.79  4954.8 1055.67
  5000.0 1054.73  5013.2 1056.29  5044.2 1055.21  5057.6 1058.05  5079.8 1058.92
  5117.6 1057.60  5124.2 1054.97  5128.2 1054.64  5128.7 1054.14  5141.1 1054.64
  5157.3 1060.95  5162.9 1060.67  5191.1 1065.61  5276.0 1069.73  5366.5 1071.73
  5394.7 1073.67  5457.0 1075.11  5551.3 1079.52  5584.2 1080.91  5612.5 1082.33
#Mann=7,-1,0
  4479.1    0.05       0  4660.2    0.12       0  4771.5    0.05       0
  5128.2    0.05       0  5141.1    0.05       0  5551.3    0.12       0
  5584.2    0.05       0
Bank Sta=5128.2,5141.1
Exp/Cntr=0.3,0.1

Type RM Length L Ch R = 1,1806,0,0,0
BEGIN DESCRIPTION:
LITTLE LLANO 055 1.0
END DESCRIPTION:
XS GIS Cut Line= 3
      2842105.68     10280003.09      2842044.00     10279757.00
      2841755.68     10279153.10
#Sta/Elev= 30
  4746.3 1070.28  4805.5 1068.91  4851.8 1067.05  4893.0 1066.53  4921.5 1062.73
  4975.4 1052.30  4983.4 1051.69  4992.9 1050.10  4993.4 1049.60  5005.4 1049.60
  5005.9 1050.10  5025.9 1052.48  5037.6 1055.24  5048.6 1056.43  5059.7 1059.31
  5070.8 1060.81  5082.4 1063.47  5105.1 1065.56  5203.8 1068.00  5241.2 1068.27
  5331.9 1067.06  5416.5 1067.87  5445.4 1068.74  5490.7 1071.05  5503.0 1072.40
  5513.4 1072.48  5525.1 1073.90  5536.1 1073.95  5609.7 1078.91  5669.2 1081.71
#Mann=4,-1,0
  4746.3    0.05       0  4992.9    0.03       0  5005.9    0.05       0
  5416.5    0.12       0
Bank Sta=4992.9,5005.9
Exp/Cntr=0.3,0.1

Chan Stop Cuts=-1