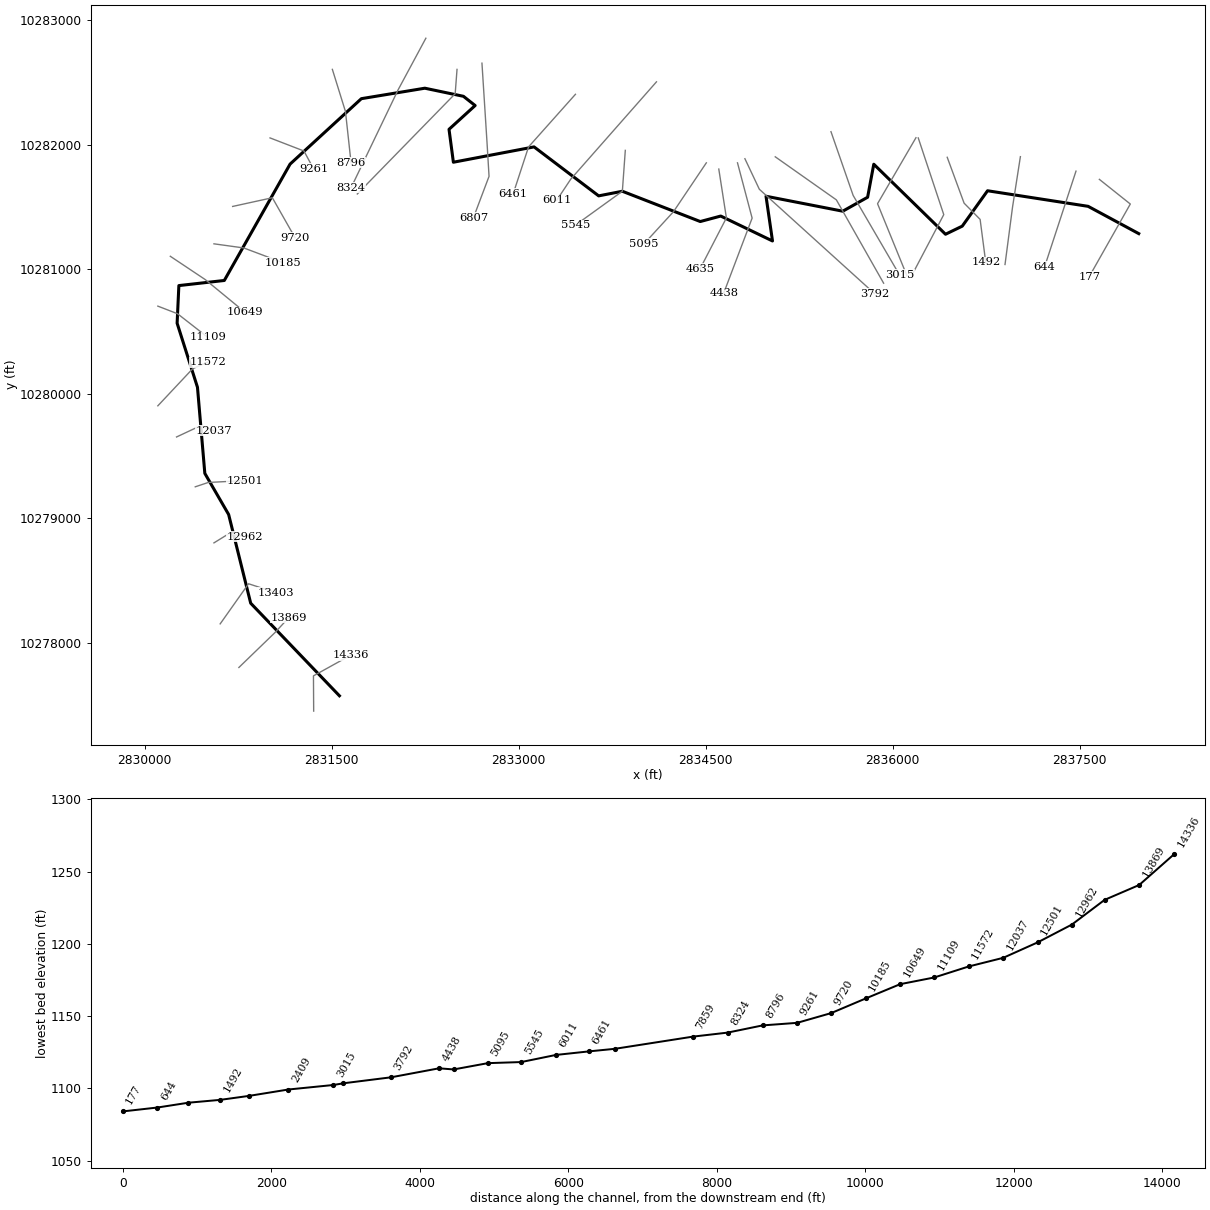
--- LITTLE LLANO 056.prj (project) ---

Proj Title=LITTLE LLANO 056 Base Level Engineering
Current Plan=p01
Default Exp/Contr=0.3,0.1
English Units
Geom File=g01
Flow File=f01
Plan File=p01
Y Axis Title=Elevation
X Axis Title(PF)=Main Channel Distance
X Axis Title(XS)=Station
BEGIN DESCRIPTION:
LITTLE LLANO 056
END DESCRIPTION:
DSS Export Rating Curves= 0
DSS Export Rating Curve Sorted= 0
DSS Export Volume Flow Curves= 0
DXF OffsetX= 0
DXF OffsetY= 0
DXF ScaleX= 1
DXF ScaleY= 10

--- LITTLE LLANO 056.p01 (plan) ---

Plan Title=Multiple Run
Short Identifier=Multiple
Geom File=g01
Flow File=f01
Subcritical Flow
K Sum by GR= 0
Std Step Tol= 0.01
Critical Tol= 0.01
Num of Std Step Trials= 20
Max Error Tol= 0.3
Flow Tol Ratio= 0.001
Split Flow NTrial= 30
Split Flow Tol= 0.02
Split Flow Ratio= 0.02
Log Output Level= 0
Friction Slope Method= 1
Unsteady Friction Slope Method= 2
Unsteady Bridges Friction Slope Method= 1
Parabolic Critical Depth
Global Vel Dist=  1 , 1 , 1
Global Log Level= 0
CheckData=True
Encroach Param= -1, 0, 0, 0
BEGIN DESCRIPTION:
Multiple Run
END DESCRIPTION:

--- LITTLE LLANO 056.f01 (steady flow) ---

Flow Title=Multiple
Number of Profiles=7
Profile Names=10-year,25-year,50-year,1pct_min,100-year,1pct_plu,500-year
River Rch & RM= LITTLE LLANO 056,Reach-1,14336
     219     338     698     611     962    1512    1408
River Rch & RM= LITTLE LLANO 056,Reach-1,9261
     623    1028    1752    1348    2422    4351    3399
River Rch & RM= LITTLE LLANO 056,Reach-1,6011
     867    1464    2443    1804    3404    6423    4754
River Rch & RM= LITTLE LLANO 056,Reach-1,1879
     910    1540    2619    1948    3659    6870    5107
Boundary for River Rch & Prof#=LITTLE LLANO 056,Reach-1,1
Up Type=0
Dn Type=3
Dn Slope=0.005
Boundary for River Rch & Prof#=LITTLE LLANO 056,Reach-1,2
Up Type=0
Dn Type=3
Dn Slope=0.005
Boundary for River Rch & Prof#=LITTLE LLANO 056,Reach-1,3
Up Type=0
Dn Type=3
Dn Slope=0.005
Boundary for River Rch & Prof#=LITTLE LLANO 056,Reach-1,4
Up Type=0
Dn Type=3
Dn Slope=0.005
Boundary for River Rch & Prof#=LITTLE LLANO 056,Reach-1,5
Up Type=0
Dn Type=3
Dn Slope=0.005
Boundary for River Rch & Prof#=LITTLE LLANO 056,Reach-1,6
Up Type=0
Dn Type=3
Dn Slope=0.005
Boundary for River Rch & Prof#=LITTLE LLANO 056,Reach-1,7
Up Type=0
Dn Type=3
Dn Slope=0.005

--- LITTLE LLANO 056.g01 (geometry) ---

Geom Title=Existing Conditions
Program Version=4.10

River Reach=LITTLE LLANO 056,Reach-1
Reach XY= 30
      2831562.25       10277576.       2830850.5       10278319.
       2830673.5       10279031.       2830482.5       10279361.
       2830423.5       10280052.      2830260.25       10280566.
      2830274.25       10280868.      2830638.75       10280909.
       2831166.5       10281843.      2831738.25       10282368.
       2832247.5       10282452.      2832557.25       10282387.
        2832651.       10282313.       2832441.5       10282122.
       2832476.5       10281858.      2833123.75       10281981.
        2833642.       10281588.        2833832.       10281625.
        2834457.       10281382.      2834621.25       10281426.
       2835036.5       10281226.       2834984.5       10281585.
      2835600.25       10281465.       2835799.5       10281577.
        2835849.       10281842.       2836424.5       10281280.
      2836558.75       10281345.      2836761.75       10281629.
       2837568.5       10281504.       2837974.5       10281285.

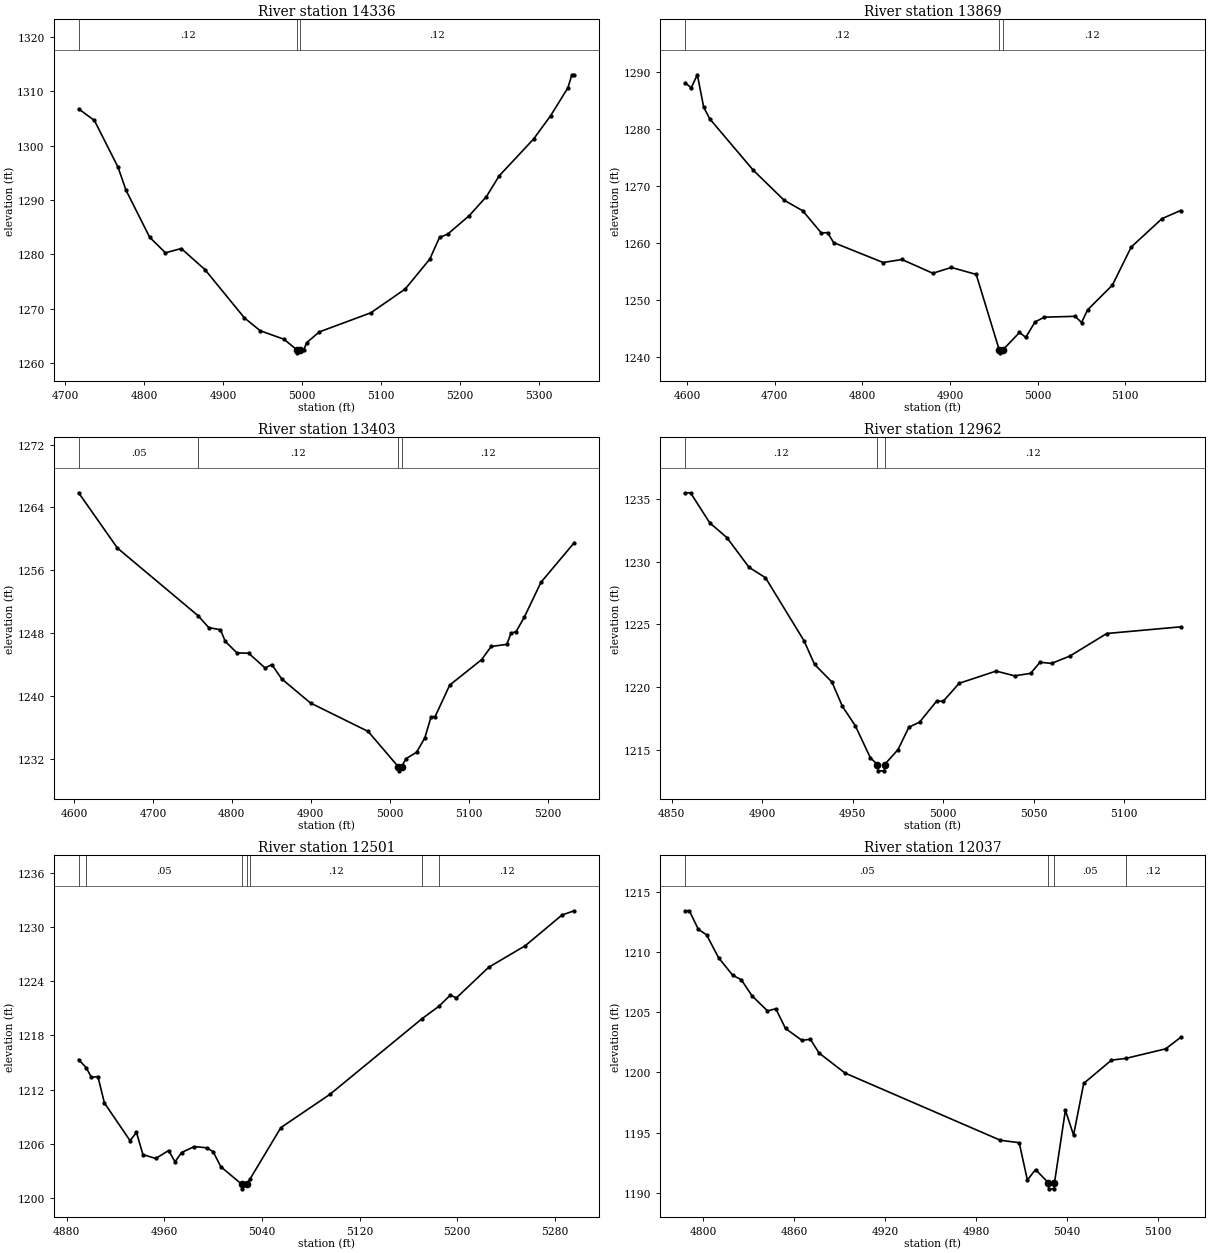
Type RM Length L Ch R = 1 ,14336   ,467,467,467
BEGIN DESCRIPTION:
LITTLE LLANO 056 30.0
END DESCRIPTION:
XS GIS Cut Line= 3
      2831355.68     10277453.11        2831354.       10277736.
       2831655.7     10277903.12
#Sta/Elev= 30
  4717.1 1306.77  4737.1 1304.64  4767.1 1296.01  4777.1 1291.81  4807.1 1283.14
  4827.1 1280.28  4847.1 1281.07  4877.1  1277.2  4927.1 1268.31  4947.1 1265.94
  4977.1 1264.38  4994.1 1262.37  4994.3 1261.87  4998.1 1262.37  5002.2 1262.37
    5006 1263.74    5022 1265.72  5087.3 1269.24  5130.8 1273.61    5162 1279.13
  5174.3 1283.12  5184.6 1283.71  5212.1 1287.14  5233.8 1290.64  5249.9 1294.45
  5293.4 1301.21  5315.1 1305.52  5336.9 1310.64    5342 1313.05  5344.9 1313.05
#Mann= 3 ,-1 , 0
  4717.1     .12       0  4994.1     .07       0  4998.1     .12       0
Bank Sta=4994.1,4998.1
XS Rating Curve= 0 ,0
Exp/Cntr=0.3,0.1

Type RM Length L Ch R = 1 ,13869   ,466,466,466
BEGIN DESCRIPTION:
LITTLE LLANO 056 29.0
END DESCRIPTION:
XS GIS Cut Line= 3
      2830755.72     10277803.14        2831045.       10278083.
      2831155.66     10278203.09
#Sta/Elev= 30
  4597.5 1288.09  4604.5 1287.21  4611.5 1289.49  4618.7 1283.82  4625.6 1281.77
  4675.3 1272.76  4710.5  1267.5  4731.9 1265.63    4753 1261.76  4760.2  1261.8
  4767.1 1260.06  4823.7 1256.57    4845  1257.1  4880.3 1254.69  4901.6  1255.7
  4929.9 1254.48  4956.2 1241.23  4956.5 1240.73  4960.2 1241.23  4979.3  1244.3
  4986.5 1243.45    4997 1246.14  5007.7 1246.99  5042.8 1247.13  5050.2 1246.04
    5057 1248.26  5085.4 1252.61  5106.9 1259.29  5142.1 1264.27  5163.3 1265.69
#Mann= 3 ,-1 , 0
  4597.5     .12       0  4956.2     .07       0  4960.2     .12       0
Bank Sta=4956.2,4960.2
XS Rating Curve= 0 ,0
Exp/Cntr=0.3,0.1

Type RM Length L Ch R = 1 ,13403   ,441,441,441
BEGIN DESCRIPTION:
LITTLE LLANO 056 28.0
END DESCRIPTION:
XS GIS Cut Line= 3
      2830605.69     10278153.12      2830833.25       10278475.
      2831055.72      10278403.1
#Sta/Elev= 30
  4605.8 1265.86    4655 1258.81  4757.4 1250.18  4770.7 1248.68  4785.5 1248.41
  4791.6 1246.93  4806.4 1245.46  4821.2 1245.42  4842.1 1243.54  4850.7 1243.97
    4863 1242.16  4899.7 1239.07  4972.7 1235.45  5011.1 1230.93  5011.3 1230.43
  5015.1 1230.93  5020.4 1231.96  5034.1  1232.8  5044.6 1234.65  5052.4  1237.3
  5057.6 1237.35  5076.1 1241.36  5116.4 1244.59  5128.7 1246.28  5148.5 1246.54
  5153.7 1247.96  5160.2 1248.17  5170.7 1250.03  5191.7 1254.45  5233.8 1259.49
#Mann= 4 ,-1 , 0
  4605.8     .05       0  4757.4     .12       0  5011.1     .07       0
  5015.1     .12       0
Bank Sta=5011.1,5015.1
XS Rating Curve= 0 ,0
Exp/Cntr=0.3,0.1

Type RM Length L Ch R = 1 ,12962   ,461,461,461
BEGIN DESCRIPTION:
LITTLE LLANO 056 27.0
END DESCRIPTION:
XS GIS Cut Line= 3
      2830555.66      10278803.1        2830677.       10278878.
      2830805.71     10278853.11
#Sta/Elev= 30
  4857.4 1235.47  4860.4 1235.47    4871 1233.08  4880.5  1231.9  4892.7 1229.54
  4901.8 1228.71  4923.1 1223.69  4928.9 1221.81  4938.5 1220.41  4944.3 1218.47
  4951.4 1216.93  4959.7 1214.39  4963.6 1213.84  4963.9 1213.34  4967.4 1213.34
  4967.6 1213.84    4975 1215.03    4981 1216.81  4986.9 1217.22  4996.3 1218.88
    5000 1218.88  5008.8 1220.31  5029.2 1221.28  5039.4  1220.9  5048.3  1221.1
  5053.4 1221.98  5059.8 1221.89    5070 1222.48  5090.3 1224.27  5131.1  1224.8
#Mann= 3 ,-1 , 0
  4857.4     .12       0  4963.6     .07       0  4967.6     .12       0
Bank Sta=4963.6,4967.6
XS Rating Curve= 0 ,0
Exp/Cntr=0.3,0.1

Type RM Length L Ch R = 1 ,12501   ,464,464,464
BEGIN DESCRIPTION:
LITTLE LLANO 056 26.0
END DESCRIPTION:
XS GIS Cut Line= 3
      2830405.72     10279253.12      2830510.25       10279288.
      2830805.66     10279303.11
#Sta/Elev= 30
  4889.8 1215.33    4896 1214.43  4900.3 1213.35  4905.6 1213.45  4910.9 1210.53
  4931.9 1206.36  4937.2 1207.26  4942.5 1204.81    4953 1204.38  4963.5 1205.26
  4968.8 1204.01  4974.1 1205.04  4984.6  1205.7    4995 1205.56    5000 1205.13
  5006.3 1203.47  5023.5 1201.52  5023.7 1201.02  5027.5 1201.52  5030.2  1202.1
  5055.5  1207.8  5095.6 1211.47  5171.3 1219.87  5184.9 1221.22  5194.3 1222.46
  5199.3 1222.16  5225.7 1225.54  5255.8 1227.94  5285.8 1231.33  5295.8  1231.8
#Mann= 7 ,-1 , 0
  4889.8     .12       0    4896     .05       0  5023.5     .05       0
  5027.5     .05       0  5030.2     .12       0  5171.3     .05       0
  5184.9     .12       0
Bank Sta=5023.5,5027.5
XS Rating Curve= 0 ,0
Exp/Cntr=0.3,0.1

Type RM Length L Ch R = 1 ,12037   ,465,465,465
BEGIN DESCRIPTION:
LITTLE LLANO 056 25.0
END DESCRIPTION:
XS GIS Cut Line= 3
      2830255.65     10279653.09      2830447.75       10279743.
      2830555.71      10279703.1
#Sta/Elev= 30
  4787.9 1213.41  4790.7 1213.41  4796.6 1211.88  4802.1 1211.41    4810 1209.51
  4819.4 1208.05    4825 1207.69  4832.1 1206.35  4842.3  1205.1  4847.8 1205.28
  4854.2 1203.64  4865.1 1202.65  4870.6 1202.75  4876.3 1201.61  4893.5 1199.94
  4996.1 1194.36  5008.5 1194.16  5013.9 1191.06  5019.3 1191.93  5027.8 1190.83
    5028 1190.33  5031.5 1190.33  5031.8 1190.83    5039 1196.85  5044.4 1194.79
  5051.1 1199.08  5069.4 1201.01    5079 1201.16  5105.2 1201.95  5115.1  1202.9
#Mann= 4 ,-1 , 0
  4787.9     .05       0  5027.8     .05       0  5031.8     .05       0
    5079     .12       0
Bank Sta=5027.8,5031.8
XS Rating Curve= 0 ,0
Exp/Cntr=0.3,0.1

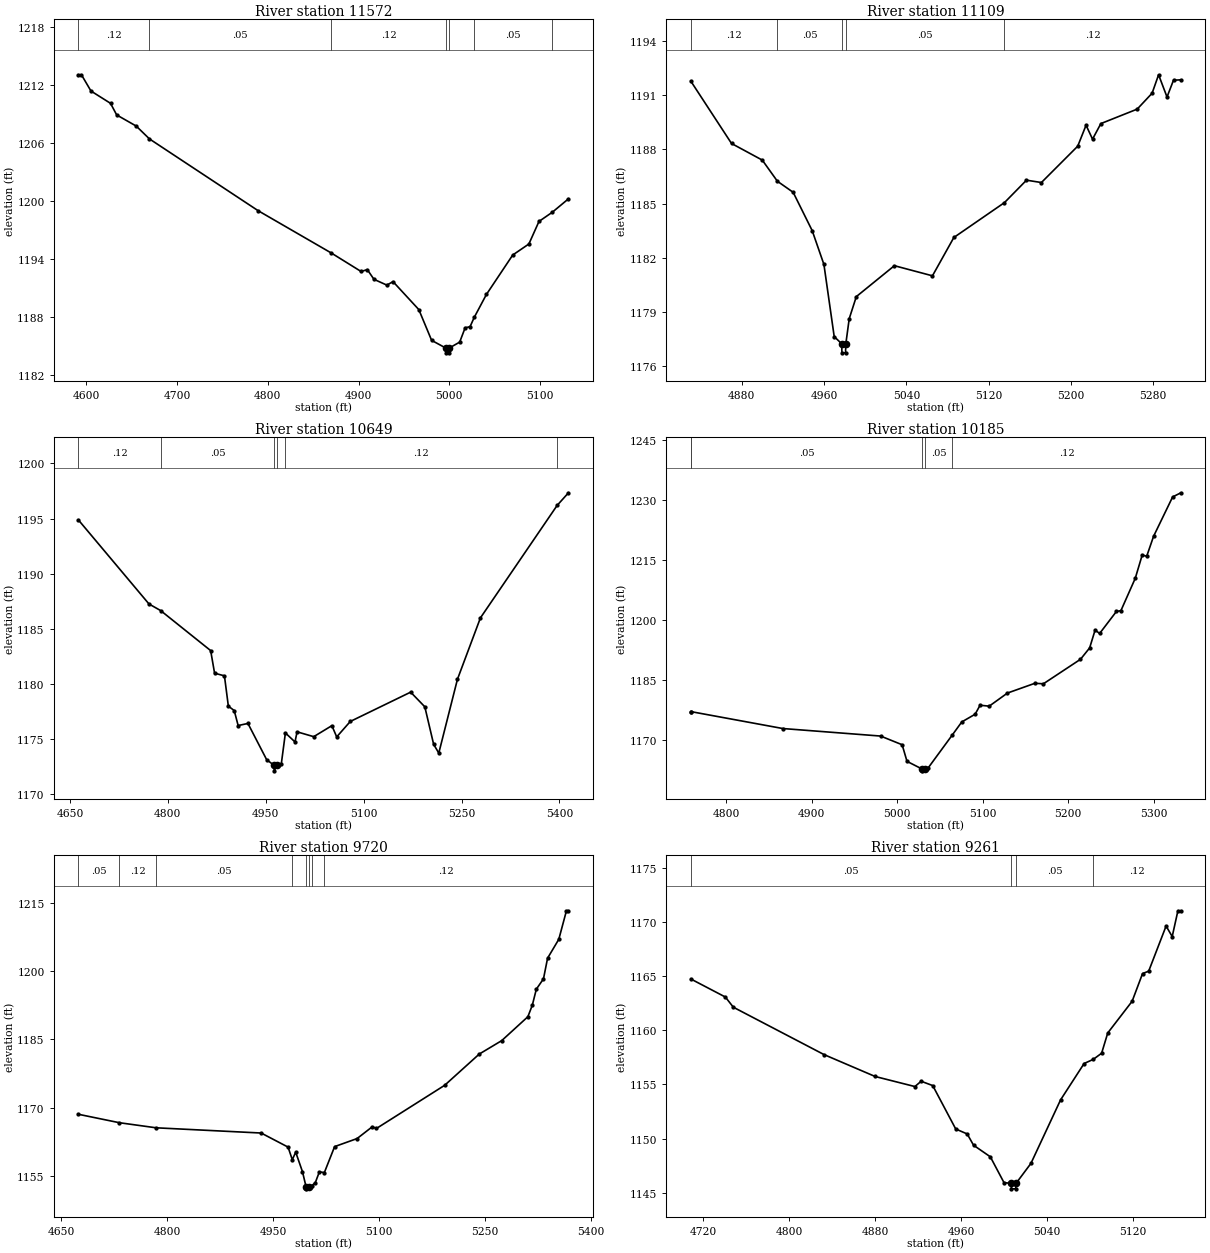
Type RM Length L Ch R = 1 ,11572   ,463,463,463
BEGIN DESCRIPTION:
LITTLE LLANO 056 24.0
END DESCRIPTION:
XS GIS Cut Line= 3
       2830105.7     10279903.13      2830385.25       10280201.
      2830505.66      10280253.1
#Sta/Elev= 30
  4591.5 1213.08  4594.9 1213.08  4605.4  1211.4  4626.9 1210.13  4633.7 1208.93
  4655.2 1207.78  4669.8 1206.45  4789.5 1199.03    4870 1194.66  4902.8 1192.75
  4909.7 1192.94    4917 1191.94  4931.2 1191.34    4938  1191.7  4966.4 1188.81
  4980.5 1185.63    4996 1184.84  4996.3 1184.34  4999.8 1184.34    5000 1184.84
  5011.4 1185.45  5017.4 1186.93  5022.8 1187.04  5027.5 1188.02  5040.8 1190.37
  5069.8 1194.45  5087.6 1195.59  5098.7 1197.92  5113.5 1198.88  5131.2 1200.26
#Mann= 7 ,-1 , 0
  4591.5     .12       0  4669.8     .05       0    4870     .12       0
    4996     .07       0    5000     .12       0  5027.5     .05       0
  5113.5     .12       0
Bank Sta=4996,5000
XS Rating Curve= 0 ,0
Exp/Cntr=0.3,0.1

Type RM Length L Ch R = 1 ,11109   ,460,460,460
BEGIN DESCRIPTION:
LITTLE LLANO 056 23.0
END DESCRIPTION:
XS GIS Cut Line= 3
      2830105.65     10280703.12      2830263.75       10280642.
      2830505.65     10280453.14
#Sta/Elev= 30
  4830.5 1191.78  4870.1 1188.33    4900 1187.41  4914.7 1186.24    4930 1185.63
  4948.5 1183.51  4959.9 1181.64  4969.9 1177.65  4977.2 1177.25  4977.4 1176.75
  4980.9 1176.75  4981.2 1177.25  4984.5 1178.64  4991.4 1179.86  5028.4 1181.57
  5065.4 1181.01  5086.2 1183.13  5135.4 1185.06  5156.8  1186.3  5171.3 1186.17
  5206.6 1188.18  5214.7 1189.34    5221 1188.57  5229.1 1189.43  5264.4 1190.23
  5278.9 1191.11  5285.2 1192.13  5293.4  1190.9  5299.7 1191.83  5306.9 1191.85
#Mann= 5 ,-1 , 0
  4830.5     .12       0  4914.7     .05       0  4977.2     .05       0
  4981.2     .05       0  5135.4     .12       0
Bank Sta=4977.2,4981.2
XS Rating Curve= 0 ,0
Exp/Cntr=0.3,0.1

Type RM Length L Ch R = 1 ,10649   ,464,464,464
BEGIN DESCRIPTION:
LITTLE LLANO 056 22.0
END DESCRIPTION:
XS GIS Cut Line= 3
      2830205.71      10281103.1        2830486.       10280916.
      2830805.69     10280653.11
#Sta/Elev= 30
    4663 1194.88  4771.2 1187.25  4789.1 1186.65  4865.7 1183.02  4871.7 1180.97
  4886.8 1180.73  4892.8 1177.98  4901.8 1177.58  4907.8 1176.22  4922.8 1176.41
  4951.5 1173.12  4962.9 1172.61  4963.1 1172.11  4966.9 1172.61  4973.9 1172.73
  4980.2 1175.55  4994.9 1174.73  4998.1 1175.65  5023.6 1175.21  5051.4 1176.21
  5058.8 1175.19  5079.6 1176.59  5172.1 1179.25  5193.8 1177.92  5207.3 1174.52
  5215.2 1173.72  5243.8 1180.42    5279 1185.99  5396.6  1196.2  5413.9 1197.34
#Mann= 6 ,-1 , 0
    4663     .12       0  4789.1     .05       0  4962.9     .07       0
  4966.9     .05       0  4980.2     .12       0  5396.6     .05       0
Bank Sta=4962.9,4966.9
XS Rating Curve= 0 ,0
Exp/Cntr=0.3,0.1

Type RM Length L Ch R = 1 ,10185   ,465,465,465
BEGIN DESCRIPTION:
LITTLE LLANO 056 21.0
END DESCRIPTION:
XS GIS Cut Line= 3
      2830555.68     10281203.11        2830795.       10281170.
      2831105.64     10281053.13
#Sta/Elev= 30
  4758.4 1176.99  4759.2 1176.99  4866.1 1172.79  4980.5 1170.91  5005.7 1168.74
  5011.4 1164.59  5028.6 1162.72  5028.9 1162.22  5032.6 1162.72  5035.9 1162.88
  5064.3 1171.15  5075.5 1174.44  5091.1 1176.36  5096.9 1178.61  5107.6 1178.38
  5128.9 1181.65    5161 1184.09    5171 1183.97  5214.4 1190.09  5225.1 1192.93
  5231.5 1197.39  5236.8 1196.54  5256.4 1202.03  5261.7 1202.24  5278.5 1210.33
  5286.6 1216.13  5291.9 1215.84  5299.9 1220.81  5322.2 1230.65  5331.9 1231.69
#Mann= 5 ,-1 , 0
  4758.4     .12       0  4759.2     .05       0  5028.6     .05       0
  5032.6     .05       0  5064.3     .12       0
Bank Sta=5028.6,5032.6
XS Rating Curve= 0 ,0
Exp/Cntr=0.3,0.1

Type RM Length L Ch R = 1 ,9720    ,459,459,459
BEGIN DESCRIPTION:
LITTLE LLANO 056 20.0
END DESCRIPTION:
XS GIS Cut Line= 3
      2830705.73     10281503.12      2831024.25       10281573.
       2831205.7     10281253.08
#Sta/Elev= 30
  4673.9 1168.52    4732 1166.66    4784 1165.54  4932.7 1164.39  4970.8 1161.29
  4976.8 1158.51  4981.6 1160.18  4991.2 1155.87  4996.2  1152.6  4996.4  1152.1
  5000.2  1152.6  5004.5 1152.82  5009.3 1153.44  5015.1 1155.83  5022.2 1155.69
  5036.7  1161.4  5068.5 1163.17  5090.1 1165.78  5095.9 1165.39  5192.5  1174.9
  5241.5 1181.78  5273.3 1184.74  5310.3    1190  5316.6 1192.54  5322.3 1196.07
  5332.4 1198.34  5338.2 1202.89  5354.1 1207.05  5364.9 1213.33  5367.8 1213.33
#Mann= 8 ,-1 , 0
  4673.9     .05       0    4732     .12       0    4784     .05       0
  4976.8     .12       0  4996.2     .07       0  5000.2     .12       0
  5004.5     .05       0  5022.2     .12       0
Bank Sta=4996.2,5000.2
XS Rating Curve= 0 ,0
Exp/Cntr=0.3,0.1

Type RM Length L Ch R = 1 ,9261    ,465,465,465
BEGIN DESCRIPTION:
LITTLE LLANO 056 19.0
END DESCRIPTION:
XS GIS Cut Line= 3
      2831005.65     10282053.12      2831277.75       10281948.
      2831355.68     10281803.13
#Sta/Elev= 30
  4708.3 1164.74  4740.5 1163.07  4747.9 1162.13  4832.4 1157.75  4879.9 1155.73
  4916.9  1154.8  4922.7 1155.29  4933.5 1154.89  4954.9 1150.88  4965.6 1150.42
  4971.5 1149.38  4987.1 1148.31  4999.8 1145.93  5006.5 1145.85  5006.8 1145.35
  5010.7 1145.35    5011 1145.85  5024.9  1147.7  5052.5 1153.57  5074.4 1156.93
  5082.9 1157.31  5090.7 1157.88  5096.4 1159.75  5119.1 1162.68  5128.8 1165.24
  5134.5 1165.46  5150.7 1169.63  5156.4 1168.66  5161.7 1171.04  5164.5 1171.04
#Mann= 4 ,-1 , 0
  4708.3     .05       0  5006.5     .03       0    5011     .05       0
  5082.9     .12       0
Bank Sta=5006.5,5011
XS Rating Curve= 0 ,0
Exp/Cntr=0.3,0.1

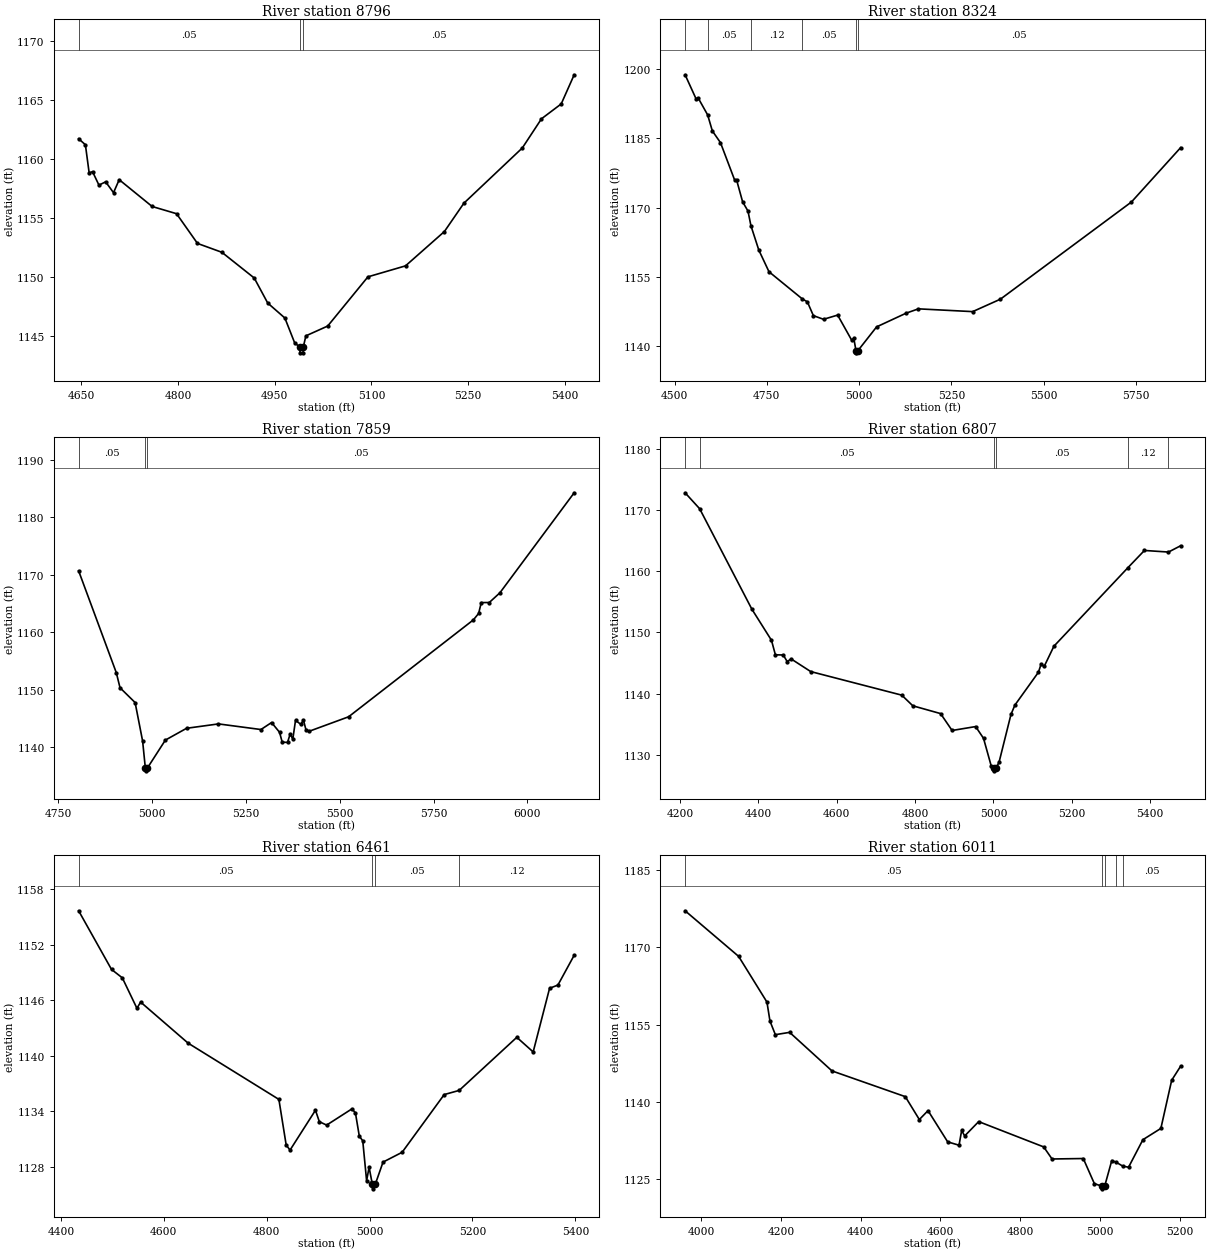
Type RM Length L Ch R = 1 ,8796    ,472,472,472
BEGIN DESCRIPTION:
LITTLE LLANO 056 18.0
END DESCRIPTION:
XS GIS Cut Line= 3
      2831505.67     10282603.15      2831610.75       10282265.
      2831655.68     10281853.14
#Sta/Elev= 30
  4645.9 1161.72  4656.4 1161.21  4662.2 1158.83  4667.5 1158.93  4677.4 1157.79
  4687.8 1158.07    4700 1157.15  4708.8 1158.25  4759.9 1155.98  4797.7 1155.37
  4830.2 1152.85    4868  1152.1  4918.2 1149.92  4939.1  1147.8  4965.7 1146.53
    4981 1144.41  4988.8 1144.08  4989.2 1143.58  4993.8 1143.58  4994.3 1144.08
  4998.3 1145.02  5032.1 1145.85  5094.5 1150.02  5152.8 1150.95  5213.1 1153.86
  5243.3 1156.26  5333.9 1160.94  5363.6 1163.41  5394.2 1164.67  5414.3 1167.14
#Mann= 3 ,-1 , 0
  4645.9     .05       0  4988.8     .03       0  4994.3     .05       0
Bank Sta=4988.8,4994.3
XS Rating Curve= 0 ,0
Exp/Cntr=0.3,0.1

Type RM Length L Ch R = 1 ,8324    ,465,465,465
BEGIN DESCRIPTION:
LITTLE LLANO 056 17.0
END DESCRIPTION:
XS GIS Cut Line= 3
      2832255.68     10282853.11       2832032.5       10282438.
      2831655.66     10281653.07
#Sta/Elev= 30
  4528.7  1198.7  4558.7 1193.45  4564.4 1193.64  4589.8 1190.02  4602.5 1186.56
  4624.5 1184.03  4662.6    1176  4668.3 1175.92  4684.5 1171.23    4699 1169.24
    4707 1166.07  4728.3 1160.81  4755.9 1156.12  4846.2 1150.24  4859.8 1149.62
  4876.1 1146.63  4903.6 1145.84  4941.8 1146.75  4979.9 1141.32  4985.6 1141.73
  4991.4 1139.09  4991.8 1138.59    4997 1139.09  5047.3  1144.2  5127.4 1147.17
  5160.6  1148.1  5307.5  1147.5  5382.6 1150.19  5737.5  1171.2  5870.7 1182.95
#Mann= 6 ,-1 , 0
  4528.7     .12       0  4589.8     .05       0    4707     .12       0
  4846.2     .05       0  4991.4     .05       0    4997     .05       0
Bank Sta=4991.4,4997
XS Rating Curve= 0 ,0
Exp/Cntr=0.3,0.1

Type RM Length L Ch R = 1 ,7859    ,1052,1052,1052
BEGIN DESCRIPTION:
LITTLE LLANO 056 16.0
END DESCRIPTION:
XS GIS Cut Line= 3
      2832505.69     10282603.15        2832491.       10282408.
       2831705.7     10281603.13
#Sta/Elev= 30
  4804.3 1170.69  4904.6 1152.95  4914.6 1150.31  4954.8 1147.73  4974.8 1141.01
    4982 1136.33  4982.5 1135.83  4987.6 1136.33  5035.4 1141.19    5092 1143.25
  5176.9 1144.01    5290 1143.03  5318.3 1144.25  5339.6 1142.55  5346.6 1140.84
  5360.8 1140.78  5367.9 1142.26  5374.9 1141.36  5382.1 1144.62  5396.2 1143.94
  5403.2 1144.68  5410.4 1142.87  5417.3  1142.7  5523.5 1145.25  5855.9 1162.14
    5870 1163.27    5877 1165.16  5898.3 1165.17  5926.6 1166.86  6124.5  1184.3
#Mann= 3 ,-1 , 0
  4804.3     .05       0    4982     .03       0  4987.6     .05       0
Bank Sta=4982,4987.6
XS Rating Curve= 0 ,0
Exp/Cntr=0.3,0.1

Type RM Length L Ch R = 1 ,6807    ,346,346,346
BEGIN DESCRIPTION:
LITTLE LLANO 056 15.0
END DESCRIPTION:
XS GIS Cut Line= 4
      2832705.69     10282653.06      2832746.91     10282006.91
      2832762.54     10281744.76      2832637.52     10281413.12
#Sta/Elev= 30
  4213.2  1172.8  4250.4 1170.19  4383.5  1153.8  4433.6 1148.71  4443.6 1146.34
  4463.7 1146.31  4473.7 1145.23  4483.7 1145.67  4533.8  1143.6  4766.1 1139.75
  4794.3 1138.01  4865.1 1136.74  4894.5 1133.98  4954.6 1134.62  4974.7  1132.7
  4994.7 1128.11  5001.8 1127.89  5002.3 1127.39  5007.6 1127.89  5014.7 1128.89
  5044.8 1136.61  5054.8 1138.13  5114.9  1143.5  5121.6 1144.82  5129.5 1144.44
  5154.3 1147.74  5343.2 1160.57  5385.3 1163.38  5446.7 1163.12  5477.7 1164.15
#Mann= 6 ,-1 , 0
  4213.2     .12       0  4250.4     .05       0  5001.8     .05       0
  5007.6     .05       0  5343.2     .12       0  5446.7     .05       0
Bank Sta=5001.8,5007.6
XS Rating Curve= 0 ,0
Exp/Cntr=0.3,0.1

Type RM Length L Ch R = 1 ,6461    ,450,450,450
BEGIN DESCRIPTION:
LITTLE LLANO 056 14.0
END DESCRIPTION:
XS GIS Cut Line= 3
      2833455.68      10282403.1       2833079.5       10281981.
      2832955.67     10281603.07
#Sta/Elev= 30
  4434.6 1155.69  4498.5 1149.35  4519.5 1148.44  4547.9 1145.15  4555.1 1145.82
  4647.4 1141.38  4823.8  1135.3    4838 1130.36  4845.5 1129.82  4894.9 1134.13
  4902.4 1132.89  4916.6 1132.52  4965.9 1134.28  4972.6 1133.83  4980.1 1131.33
  4986.8 1130.82  4994.3  1126.5  4999.1 1127.97  5005.4 1126.13  5005.9 1125.63
  5011.2 1126.13  5026.2 1128.52  5063.3 1129.58  5145.1 1135.82  5174.2 1136.27
  5286.2 1142.01    5318 1140.43  5349.9 1147.31  5366.1 1147.66  5397.7 1150.88
#Mann= 4 ,-1 , 0
  4434.6     .05       0  5005.4     .05       0  5011.2     .05       0
  5174.2     .12       0
Bank Sta=5005.4,5011.2
XS Rating Curve= 0 ,0
Exp/Cntr=0.3,0.1

Type RM Length L Ch R = 1 ,6011    ,466,466,466
BEGIN DESCRIPTION:
LITTLE LLANO 056 13.0
END DESCRIPTION:
XS GIS Cut Line= 3
      2834105.69     10282503.12        2833418.       10281722.
       2833305.7     10281553.13
#Sta/Elev= 30
  3959.3 1177.07  4093.6 1168.23  4164.7 1159.36  4172.3 1155.67  4185.8 1153.04
  4221.6 1153.49  4327.9 1146.01  4511.9 1141.02  4547.1 1136.58  4568.9 1138.31
  4618.2 1132.25  4646.7  1131.6  4653.3 1134.46  4660.9  1133.4    4696 1136.18
  4859.2 1131.27  4880.1 1128.93  4958.5 1129.02  4986.3 1124.15  5005.8 1123.64
  5006.3 1123.14  5012.1 1123.64    5030 1128.63  5041.1 1128.29  5057.3 1127.56
  5072.1 1127.33  5108.1 1132.67  5153.2 1134.86  5180.3  1144.2  5202.8 1146.93
#Mann= 5 ,-1 , 0
  3959.3     .05       0  5005.8     .05       0  5012.1     .05       0
  5041.1     .12       0  5057.3     .05       0
Bank Sta=5005.8,5012.1
XS Rating Curve= 0 ,0
Exp/Cntr=0.3,0.1

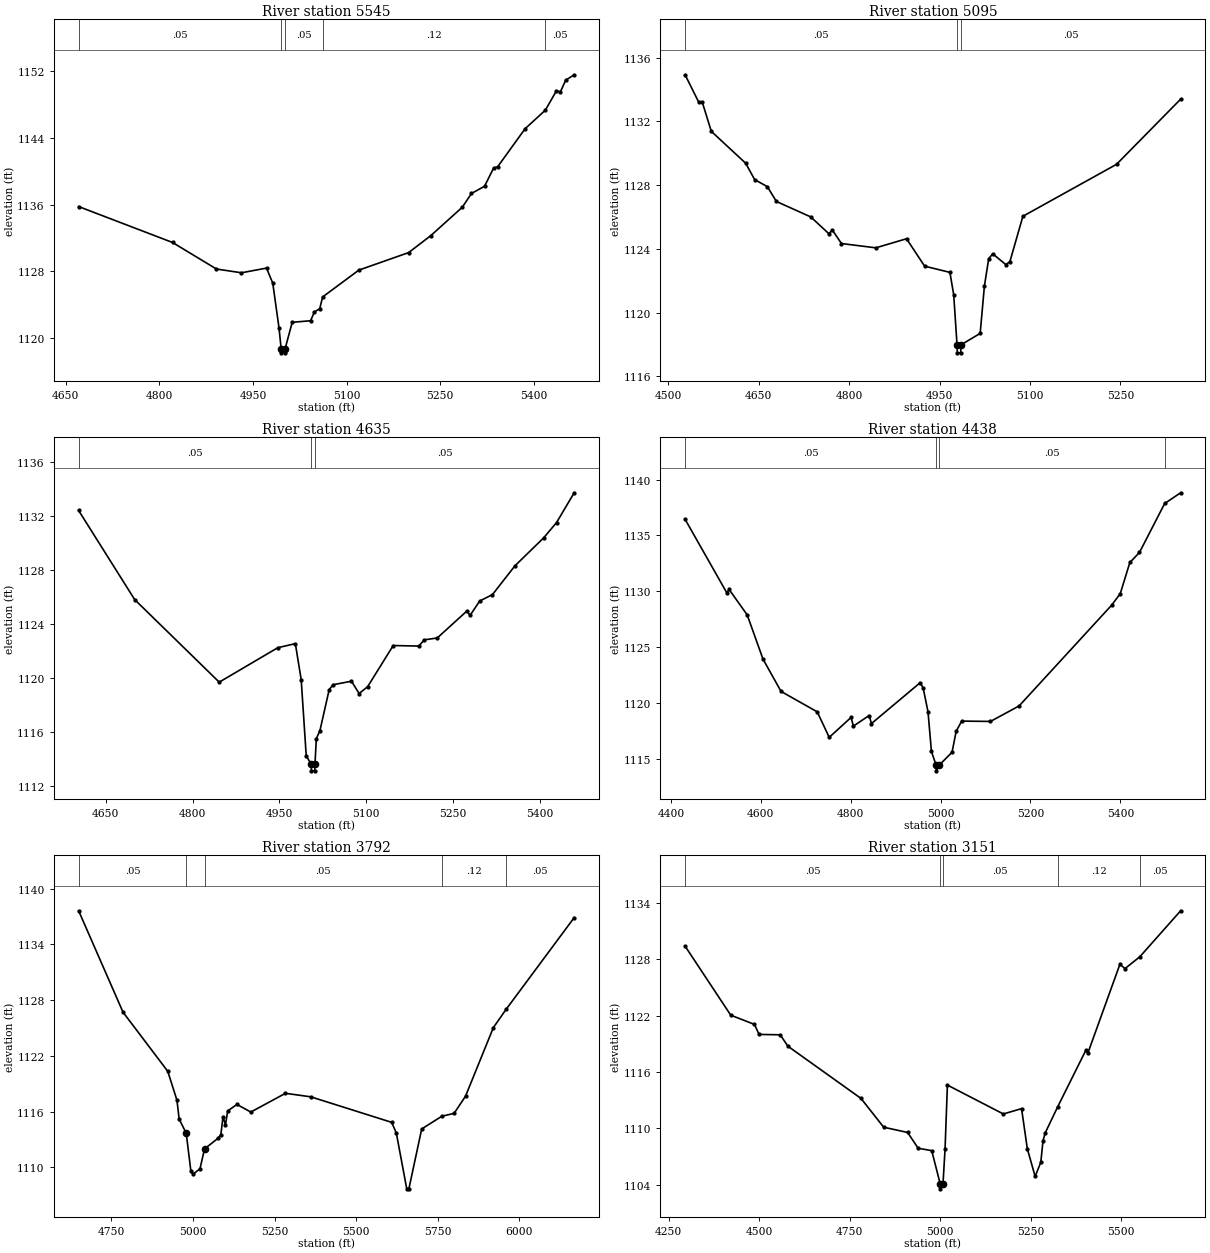
Type RM Length L Ch R = 1 ,5545    ,450,450,450
BEGIN DESCRIPTION:
LITTLE LLANO 056 12.0
END DESCRIPTION:
XS GIS Cut Line= 3
      2833855.69     10281953.15        2833832.       10281625.
      2833455.65     10281353.09
#Sta/Elev= 30
    4671 1135.77  4821.4 1131.46  4891.6 1128.28  4931.7 1127.83  4971.8 1128.39
  4981.8 1126.58  4991.9 1121.15  4995.2 1118.73  4995.7 1118.23  5001.1 1118.23
  5001.6 1118.73  5012.9 1121.89  5042.3 1122.08  5048.4 1123.12    5057 1123.53
  5061.6 1124.93  5119.6 1128.15  5199.3 1130.25  5234.9 1132.29  5285.2 1135.69
  5299.9 1137.34  5320.8  1138.2  5335.5 1140.41  5341.6 1140.52  5385.7  1145.1
  5418.2 1147.33    5436 1149.66  5442.2 1149.51  5450.7 1150.92  5464.3 1151.57
#Mann= 5 ,-1 , 0
    4671     .05       0  4995.2     .03       0  5001.6     .05       0
  5061.6     .12       0  5418.2     .05       0
Bank Sta=4995.2,5001.6
XS Rating Curve= 0 ,0
Exp/Cntr=0.3,0.1

Type RM Length L Ch R = 1 ,5095    ,460,460,460
BEGIN DESCRIPTION:
LITTLE LLANO 056 11.0
END DESCRIPTION:
XS GIS Cut Line= 3
      2834505.69     10281853.12      2834242.25       10281461.
      2834005.66     10281203.08
#Sta/Elev= 30
  4527.6 1134.92  4550.1 1133.21  4556.1  1133.2  4571.1 1131.37  4628.1 1129.37
  4643.1 1128.34  4664.1  1127.9  4679.1 1126.97  4736.1    1126  4766.1 1124.95
  4772.1 1125.17  4787.1 1124.33  4844.1 1124.06  4895.1 1124.63  4925.1 1122.91
  4967.1 1122.52  4973.4 1121.11  4978.9 1117.97  4979.4 1117.47  4984.9 1117.47
  4985.4 1117.97  5017.3 1118.69  5024.3 1121.65  5031.5 1123.39  5038.3 1123.68
  5059.8 1123.01  5066.6 1123.19  5088.2 1126.04  5243.6  1129.3    5350 1133.39
#Mann= 3 ,-1 , 0
  4527.6     .05       0  4978.9     .03       0  4985.4     .05       0
Bank Sta=4978.9,4985.4
XS Rating Curve= 0 ,0
Exp/Cntr=0.3,0.1

Type RM Length L Ch R = 1 ,4635    ,197,197,197
BEGIN DESCRIPTION:
LITTLE LLANO 056 10.0
END DESCRIPTION:
XS GIS Cut Line= 3
      2834605.69     10281803.07      2834666.75       10281411.
      2834455.67     10281003.08
#Sta/Elev= 30
  4603.2 1132.38    4700 1125.79  4846.1 1119.68  4947.3 1122.23  4977.6 1122.53
  4987.7 1119.87  4996.4 1114.23  5004.9 1113.62  5005.4 1113.12    5011 1113.12
  5011.5 1113.62  5013.9 1115.51  5020.1  1116.1    5036 1119.12  5042.7 1119.49
  5074.6 1119.75  5087.7 1118.84  5102.4 1119.34  5146.7 1122.39    5191 1122.35
  5200.3 1122.81  5222.8 1122.95  5273.9 1124.94  5279.5 1124.62    5296 1125.68
  5318.2 1126.16  5356.8 1128.28  5406.7 1130.36  5428.9 1131.49  5459.3 1133.69
#Mann= 3 ,-1 , 0
  4603.2     .05       0  5004.9     .03       0  5011.5     .05       0
Bank Sta=5004.9,5011.5
XS Rating Curve= 0 ,0
Exp/Cntr=0.3,0.1

Type RM Length L Ch R = 1 ,4438    ,646,646,646
BEGIN DESCRIPTION:
LITTLE LLANO 056 9.0
END DESCRIPTION:
XS GIS Cut Line= 3
      2834755.69      10281853.1      2834873.06     10281409.46
      2834645.18     10280807.45
#Sta/Elev= 30
  4431.5 1136.45  4524.3 1129.86  4529.5 1130.16  4569.7 1127.88  4604.8 1123.92
    4645 1121.02  4725.5 1119.19  4752.2  1116.9  4800.8 1118.69    4806 1117.91
    4841 1118.86  4846.2 1118.14  4954.8 1121.81  4961.3 1121.31    4972 1119.19
  4979.6 1115.64  4990.1  1114.4  4990.6  1113.9  4996.7  1114.4  5025.5 1115.57
  5034.6 1117.44  5046.9 1118.36    5111 1118.33  5174.7 1119.72  5380.5 1128.75
  5399.7 1129.78  5421.1 1132.58  5442.5 1133.48  5498.6 1137.87  5534.1 1138.83
#Mann= 4 ,-1 , 0
  4431.5     .05       0  4990.1     .03       0  4996.7     .05       0
  5498.6     .12       0
Bank Sta=4990.1,4996.7
XS Rating Curve= 0 ,0
Exp/Cntr=0.3,0.1

Type RM Length L Ch R = 1 ,3792    ,641,641,641
BEGIN DESCRIPTION:
LITTLE LLANO 056 8.0
END DESCRIPTION:
XS GIS Cut Line= 3
      2834815.18     10281886.12      2834930.94     10281640.99
      2835855.71     10280803.09
#Sta/Elev= 30
  4649.4 1137.63  4785.4 1126.71  4922.6 1120.34  4950.8 1117.22  4957.6 1115.19
  4979.2 1113.67  4993.4 1109.62  5000.2 1109.26  5021.4 1109.84  5035.3 1111.98
  5077.9 1113.16  5085.3 1113.52  5092.1 1115.45  5099.5 1114.56  5106.3 1116.07
  5134.7 1116.77  5177.2 1115.95  5283.4 1117.97  5361.1 1117.59  5609.1 1114.84
  5623.3 1113.68  5655.2 1107.68  5661.7 1107.68    5701 1114.13  5762.7  1115.5
  5800.4 1115.81  5835.5 1117.67  5920.7 1125.05  5959.7 1127.01  6168.4 1136.89
#Mann= 5 ,-1 , 0
  4649.4     .05       0  4979.2     .03       0  5035.3     .05       0
  5762.7     .12       0  5959.7     .05       0
Bank Sta=4979.2,5035.3
XS Rating Curve= 0 ,0
Exp/Cntr=0.3,0.1

Type RM Length L Ch R = 1 ,3151    ,136,136,136
BEGIN DESCRIPTION:
LITTLE LLANO 056 7.0
END DESCRIPTION:
XS GIS Cut Line= 3
      2835058.65     10281901.44      2835548.92     10281555.87
      2835927.97     10280887.15
#Sta/Elev= 30
  4295.8 1129.42  4421.9 1122.06  4487.2 1121.08  4500.2 1120.01  4558.6 1119.97
  4579.5 1118.76  4781.5 1113.19  4844.2 1110.12  4910.3 1109.56  4939.4 1107.88
  4976.9 1107.62  5000.5 1104.05    5001 1103.55    5008 1104.05  5013.7 1107.79
  5020.2 1114.61  5174.7 1111.53    5225  1112.1  5240.9 1107.82  5262.5 1104.87
  5278.1 1106.38  5284.2 1108.65  5289.9 1109.48  5324.7 1112.29  5402.5 1118.32
  5408.2 1118.03  5496.5 1127.48  5510.7 1127.03  5551.4 1128.28  5664.3 1133.19
#Mann= 5 ,-1 , 0
  4295.8     .05       0  5000.5     .03       0    5008     .05       0
  5324.7     .12       0  5551.4     .05       0
Bank Sta=5000.5,5008
XS Rating Curve= 0 ,0
Exp/Cntr=0.3,0.1

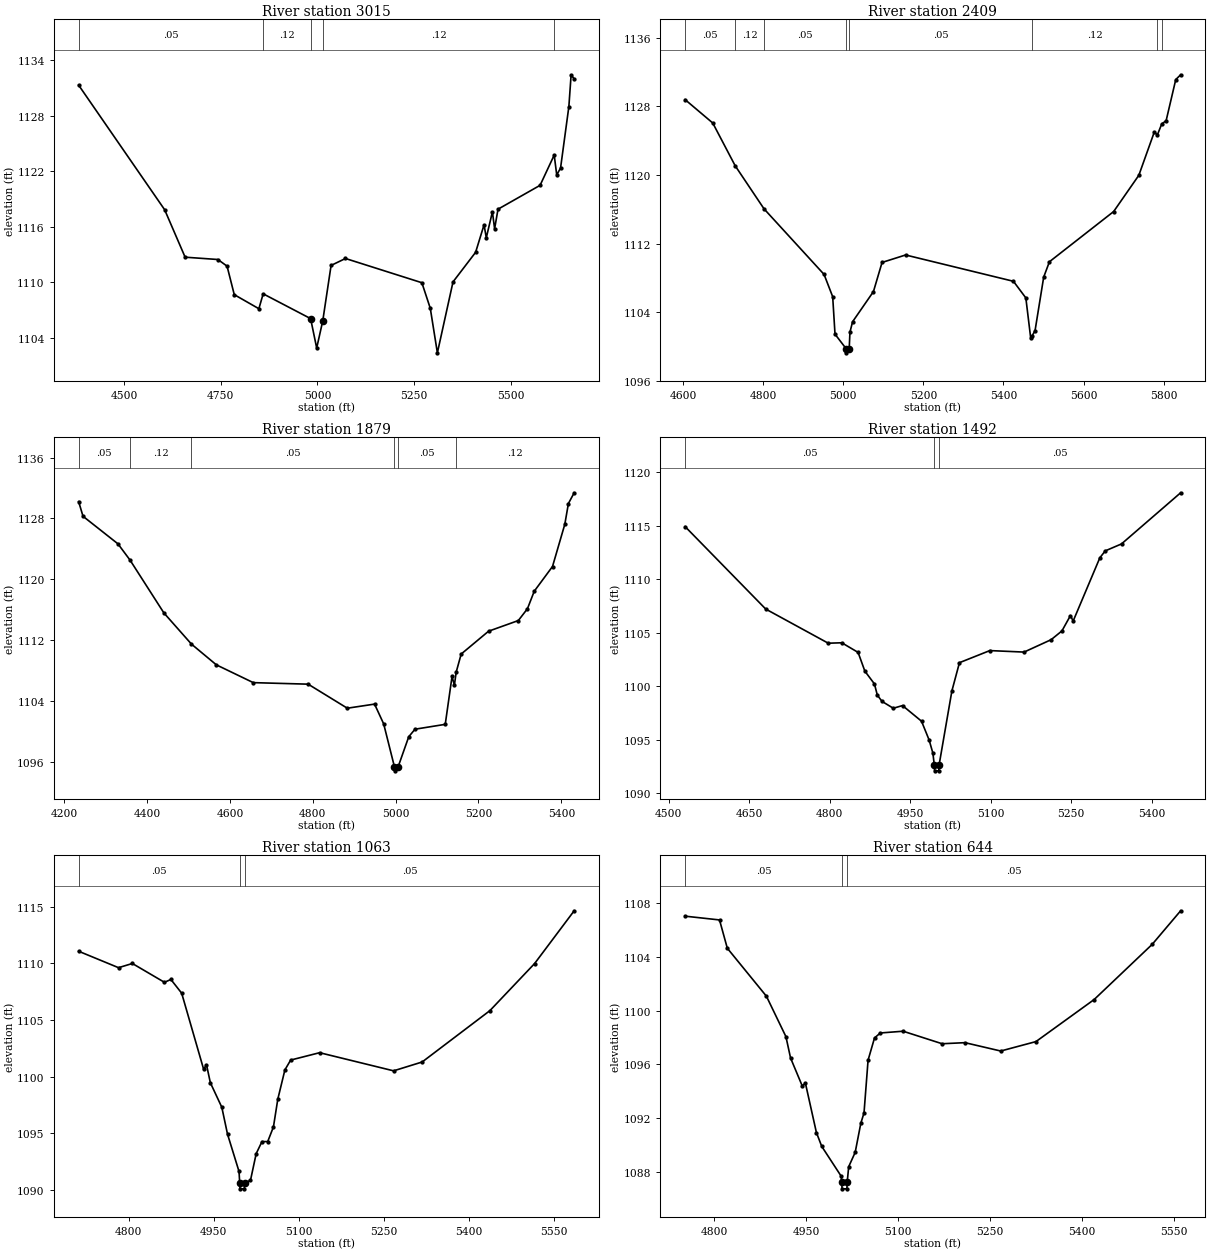
Type RM Length L Ch R = 1 ,3015    ,606,606,606
BEGIN DESCRIPTION:
LITTLE LLANO 056 6.0
END DESCRIPTION:
XS GIS Cut Line= 3
       2835505.7     10282103.07      2835683.41     10281591.62
      2836055.71     10280953.08
#Sta/Elev= 30
  4382.8  1131.3  4605.1 1117.83    4658  1112.7  4742.7 1112.45  4766.4 1111.73
    4785 1108.65  4848.6 1107.13  4859.7 1108.74  4982.3 1106.06    4998 1102.88
  5013.7 1105.82  5035.2 1111.81  5072.4 1112.56  5269.8 1109.94  5291.6 1107.17
  5309.9 1102.36  5350.3 1110.03  5408.7 1113.23  5430.5  1116.2  5436.3  1114.8
  5452.1  1117.6  5457.8 1115.77  5466.6 1117.89  5575.3 1120.47  5611.8 1123.74
  5618.3  1121.6  5628.2 1122.33  5649.7 1128.99  5655.5 1132.42  5663.4 1131.97
#Mann= 5 ,-1 , 0
  4382.8     .05       0  4859.7     .12       0  4982.3     .03       0
  5013.7     .12       0  5611.8     .05       0
Bank Sta=4982.3,5013.7
XS Rating Curve= 0 ,0
Exp/Cntr=0.3,0.1

Type RM Length L Ch R = 1 ,2409    ,530,530,530
BEGIN DESCRIPTION:
LITTLE LLANO 056 5.0
END DESCRIPTION:
XS GIS Cut Line= 3
      2836187.31     10282054.65      2835879.19     10281525.22
      2836115.12     10280946.42
#Sta/Elev= 30
    4605 1128.79  4674.1 1126.06  4730.1 1121.07  4802.2 1116.04  4952.1 1108.39
  4973.6 1105.79  4979.4 1101.42  5006.9 1099.74  5007.4 1099.24  5014.9 1099.74
  5016.7 1101.65  5023.3 1102.87  5075.4 1106.39  5096.9 1109.79  5155.7 1110.66
    5425 1107.59    5456 1105.65  5468.2 1100.94  5471.6 1101.22    5479 1101.83
  5500.6 1108.08  5514.9 1109.87  5675.3 1115.73  5738.2 1119.96  5776.9 1125.02
  5784.4 1124.66  5795.3 1125.94  5806.4 1126.34  5830.4 1131.13  5842.6 1131.69
#Mann= 8 ,-1 , 0
    4605     .05       0  4730.1     .12       0  4802.2     .05       0
  5006.9     .05       0  5014.9     .05       0  5471.6     .12       0
  5784.4     .05       0  5795.3     .12       0
Bank Sta=5006.9,5014.9
XS Rating Curve= 0 ,0
Exp/Cntr=0.3,0.1

Type RM Length L Ch R = 1 ,1879    ,387,387,387
BEGIN DESCRIPTION:
LITTLE LLANO 056 4.0
END DESCRIPTION:
XS GIS Cut Line= 3
      2836205.68     10282053.13       2836410.4     10281437.47
      2836155.66     10280953.07
#Sta/Elev= 30
  4234.9 1130.21  4245.5 1128.28  4329.8 1124.66  4358.9 1122.53  4440.7 1115.58
  4507.3 1111.48  4567.3 1108.76  4656.5 1106.42  4788.9 1106.22  4883.4 1103.06
  4949.2  1103.6  4971.2    1101  4997.3 1095.33  4997.8 1094.83  5005.9 1095.33
  5031.7 1099.31  5046.8  1100.3  5119.8 1100.94  5136.2 1107.23  5141.9 1106.09
  5146.2  1107.8  5158.3 1110.18  5224.4 1113.18  5296.2 1114.58  5318.2 1116.13
  5334.6 1118.43  5378.7 1121.68  5408.4 1127.23  5417.1 1129.96    5431 1131.37
#Mann= 6 ,-1 , 0
  4234.9     .05       0  4358.9     .12       0  4507.3     .05       0
  4997.3     .03       0  5005.9     .05       0  5146.2     .12       0
Bank Sta=4997.3,5005.9
XS Rating Curve= 0 ,0
Exp/Cntr=0.3,0.1

Type RM Length L Ch R = 1 ,1492    ,429,429,429
BEGIN DESCRIPTION:
LITTLE LLANO 056 3.0
END DESCRIPTION:
XS GIS Cut Line= 4
      2836438.18     10281897.53      2836573.59     10281529.48
      2836702.06     10281399.27       2836747.2      10281053.8
#Sta/Elev= 30
  4530.8 1114.91  4681.1  1107.2  4797.6 1104.01  4822.8 1104.05  4853.2 1103.15
  4865.8  1101.4  4883.7  1100.2    4889 1099.16  4897.8 1098.57  4918.8 1097.93
    4936 1098.18  4971.4 1096.72  4985.6 1094.96  4992.6 1093.73  4995.3 1092.58
  4995.8 1092.08  5003.5 1092.08    5004 1092.58    5028 1099.55  5042.1 1102.19
  5098.7 1103.32  5162.5 1103.18    5213 1104.34  5233.1 1105.16  5248.9 1106.59
    5254 1106.08  5303.7 1111.99  5313.8 1112.64  5344.1 1113.29  5454.3 1118.07
#Mann= 3 ,-1 , 0
  4530.8     .05       0  4995.3     .05       0    5004     .05       0
Bank Sta=4995.3,5004
XS Rating Curve= 0 ,0
Exp/Cntr=0.3,0.1

Type RM Length L Ch R = 1 ,1063    ,419,419,419
BEGIN DESCRIPTION:
LITTLE LLANO 056 2.0
END DESCRIPTION:
XS GIS Cut Line= 3
      2837025.12     10281902.72      2836962.18     10281498.27
      2836901.82     10281037.22
#Sta/Elev= 30
  4711.7 1111.07  4782.1 1109.62  4806.5 1109.99  4863.1 1108.33  4874.5 1108.58
  4893.5 1107.37  4932.3 1100.65  4937.3 1101.06  4944.1 1099.47  4964.3 1097.31
  4974.4 1094.93  4994.7 1091.64  4995.9 1090.61  4996.4 1090.11  5004.1 1090.11
  5004.6 1090.61  5014.9 1090.86    5025 1093.22  5035.2 1094.28  5045.3 1094.28
  5055.4 1095.57  5063.1 1098.02  5075.6  1100.6  5085.8 1101.47  5136.9 1102.12
  5267.4 1100.52  5317.8  1101.3  5437.3 1105.83  5516.1 1109.98    5586 1114.64
#Mann= 3 ,-1 , 0
  4711.7     .05       0  4995.9     .05       0  5004.6     .05       0
Bank Sta=4995.9,5004.6
XS Rating Curve= 0 ,0
Exp/Cntr=0.3,0.1

Type RM Length L Ch R = 1 ,644     ,467,467,467
BEGIN DESCRIPTION:
Mapping XS dba67895
END DESCRIPTION:
XS GIS Cut Line= 2
      2837471.17     10281786.46      2837219.44      10281019.1
#Sta/Elev= 30
  4752.9 1107.01    4809 1106.73  4821.7 1104.63  4885.4 1101.07  4917.2 1098.07
  4924.8 1096.48  4943.8 1094.41    4949 1094.61  4966.9 1090.95  4975.6 1089.92
  5007.4  1087.7  5008.2 1087.27  5008.7 1086.77  5016.6 1086.77  5017.1 1087.27
  5019.5 1088.41  5030.1 1089.48  5039.3 1091.64  5044.5 1092.41  5051.1 1096.32
  5061.6 1097.97  5071.1 1098.34  5108.2 1098.47  5171.8 1097.54    5209 1097.62
  5267.3    1097  5324.7  1097.7  5419.5 1100.82  5514.2 1104.92  5560.5 1107.41
#Mann= 3 ,-1 , 0
  4752.9     .05       0  5008.2     .03       0  5017.1     .05       0
Bank Sta=5008.2,5017.1
XS Rating Curve= 0 ,0
Exp/Cntr=0.3,0.1

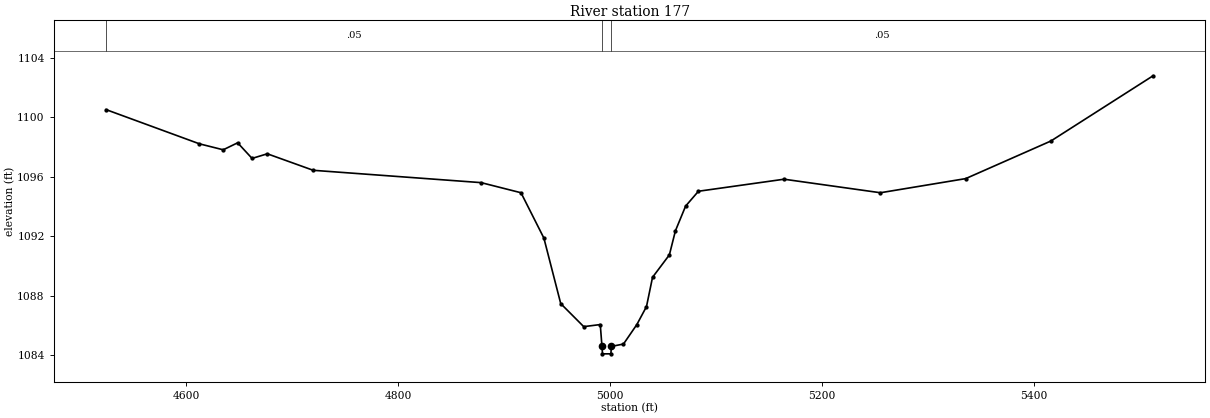
Type RM Length L Ch R = 1 ,177     ,0,0,0
BEGIN DESCRIPTION:
LITTLE LLANO 056 1.0
END DESCRIPTION:
XS GIS Cut Line= 3
       2837658.7     10281720.42      2837906.93     10281522.54
      2837577.06     10280939.19
#Sta/Elev= 30
  4524.8 1100.51  4612.8 1098.21  4635.2 1097.81  4648.8 1098.28  4662.4 1097.23
  4676.8 1097.54  4720.1 1096.43  4878.5  1095.6  4916.1 1094.92  4937.7 1091.87
  4953.6 1087.46  4975.3 1085.91  4990.9 1086.05  4992.5 1084.58    4993 1084.08
  5000.9 1084.08  5001.4 1084.58  5012.8 1084.74  5025.4 1086.05  5034.5 1087.26
  5040.2 1089.23  5056.1 1090.74  5061.8 1092.36  5071.4 1094.02  5083.5 1095.02
  5164.3 1095.83  5255.2 1094.92  5335.6 1095.87    5416  1098.4  5512.4 1102.79
#Mann= 3 ,-1 , 0
  4524.8     .05       0  4992.5     .03       0  5001.4     .05       0
Bank Sta=4992.5,5001.4
XS Rating Curve= 0 ,0
Exp/Cntr=0.3,0.1

Chan Stop Cuts=-1
Use User Specified Reach Order=0
Composite Channel Slope=5