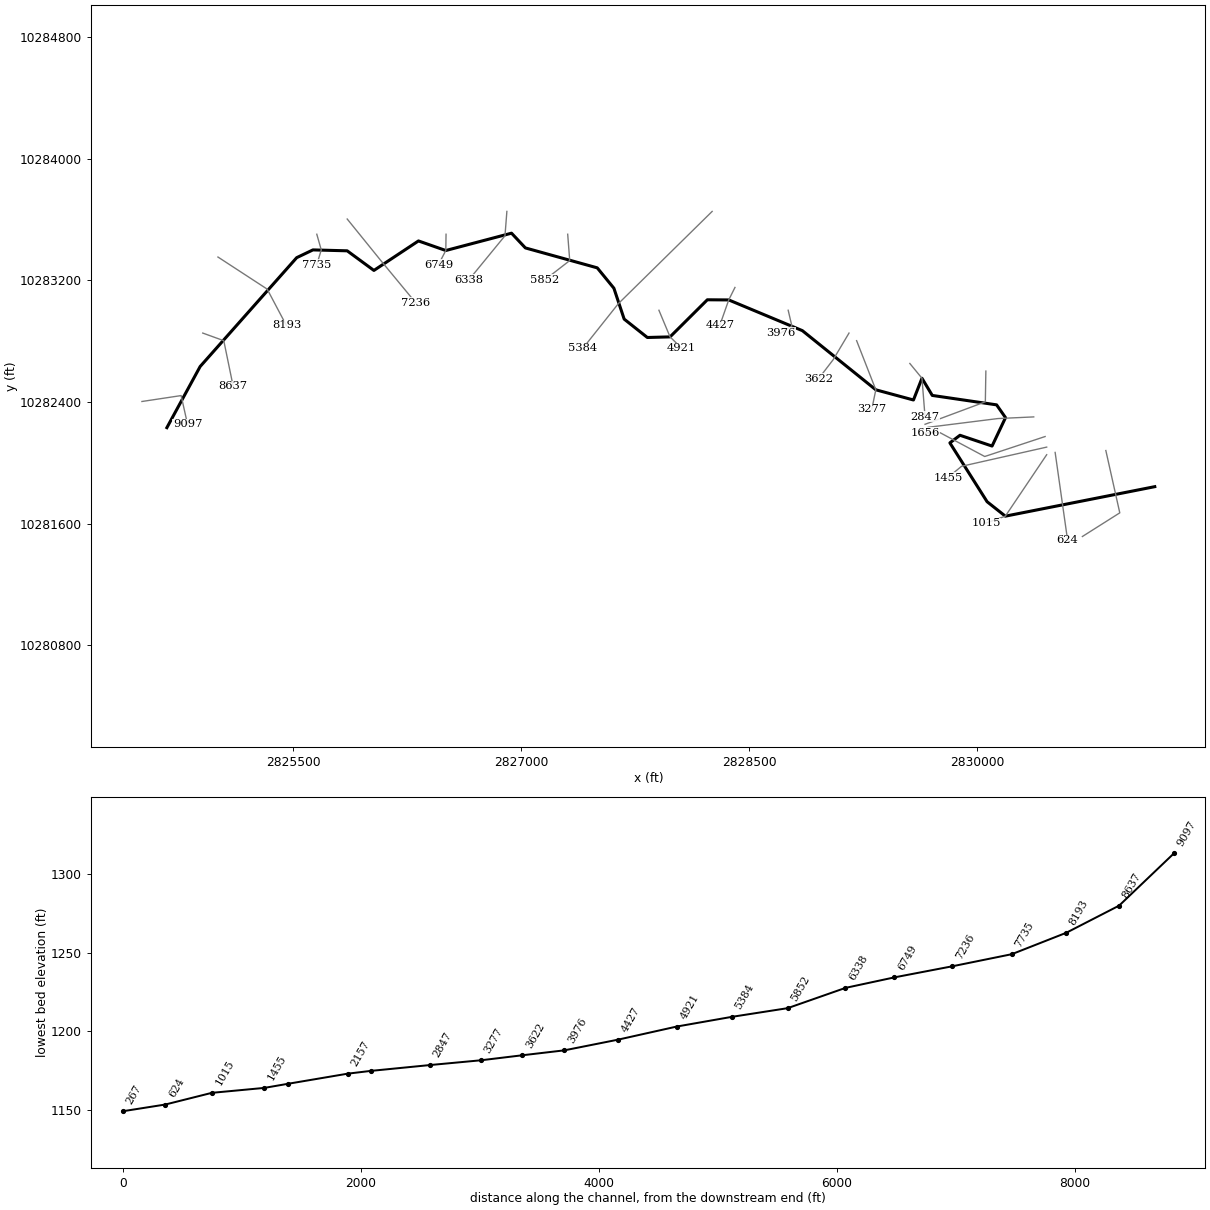
--- LITTLE LLANO 057.prj (project) ---

Proj Title=LITTLE LLANO 057 Base Level Engineering
Current Plan=p01
Default Exp/Contr=0.3,0.1
English Units
Geom File=g01
Flow File=f01
Plan File=p01
Y Axis Title=Elevation
X Axis Title(PF)=Main Channel Distance
X Axis Title(XS)=Station
BEGIN DESCRIPTION:
LITTLE LLANO 057
END DESCRIPTION:
DSS Export Rating Curves= 0
DSS Export Rating Curve Sorted= 0
DSS Export Volume Flow Curves= 0
DXF OffsetX= 0
DXF OffsetY= 0
DXF ScaleX= 1
DXF ScaleY= 10

--- LITTLE LLANO 057.p01 (plan) ---

Plan Title=Multiple Run
Short Identifier=Multiple
Geom File=g01
Flow File=f01
Subcritical Flow
K Sum by GR= 0
Std Step Tol= 0.01
Critical Tol= 0.01
Num of Std Step Trials= 20
Max Error Tol= 0.3
Flow Tol Ratio= 0.001
Split Flow NTrial= 30
Split Flow Tol= 0.02
Split Flow Ratio= 0.02
Log Output Level= 0
Friction Slope Method= 1
Unsteady Friction Slope Method= 2
Unsteady Bridges Friction Slope Method= 1
Parabolic Critical Depth
Global Vel Dist=  1 , 1 , 1
Global Log Level= 0
CheckData=True
Encroach Param= -1, 0, 0, 0
BEGIN DESCRIPTION:
Multiple Run
END DESCRIPTION:

--- LITTLE LLANO 057.f01 (steady flow) ---

Flow Title=Multiple
Number of Profiles=7
Profile Names=10-year,25-year,50-year,1pct_min,100-year,1pct_plu,500-year
River Rch & RM= LITTLE LLANO 057,Reach-1,9097
     351     555     996     848    1358    2175    1918
River Rch & RM= LITTLE LLANO 057,Reach-1,2348
     439     707    1221     982    1673    2851    2358
River Rch & RM= LITTLE LLANO 057,Reach-1,267
     623    1028    1752    1348    2422    4351    3399
Boundary for River Rch & Prof#=LITTLE LLANO 057,Reach-1,1
Up Type=0
Dn Type=3
Dn Slope=0.005
Boundary for River Rch & Prof#=LITTLE LLANO 057,Reach-1,2
Up Type=0
Dn Type=3
Dn Slope=0.005
Boundary for River Rch & Prof#=LITTLE LLANO 057,Reach-1,3
Up Type=0
Dn Type=3
Dn Slope=0.005
Boundary for River Rch & Prof#=LITTLE LLANO 057,Reach-1,4
Up Type=0
Dn Type=3
Dn Slope=0.005
Boundary for River Rch & Prof#=LITTLE LLANO 057,Reach-1,5
Up Type=0
Dn Type=3
Dn Slope=0.005
Boundary for River Rch & Prof#=LITTLE LLANO 057,Reach-1,6
Up Type=0
Dn Type=3
Dn Slope=0.005
Boundary for River Rch & Prof#=LITTLE LLANO 057,Reach-1,7
Up Type=0
Dn Type=3
Dn Slope=0.005

--- LITTLE LLANO 057.g01 (geometry) ---

Geom Title=Existing Conditions
Program Version=4.10

River Reach=LITTLE LLANO 057,Reach-1
Reach XY= 30
      2824669.75       10282231.       2824888.5       10282633.
       2825523.5       10283349.      2825630.25       10283400.
       2825855.5       10283394.      2826031.25       10283265.
      2826324.25       10283459.        2826504.       10283396.
      2826936.25       10283510.       2827027.5       10283413.
        2827500.       10283282.       2827609.5       10283148.
        2827677.       10282945.       2827829.5       10282824.
      2827978.75       10282828.        2828224.       10283072.
      2828364.75       10283071.        2828849.       10282869.
        2829332.       10282480.       2829579.5       10282413.
       2829635.5       10282556.      2829703.25       10282443.
      2830126.25       10282381.        2830185.       10282297.
       2830096.5       10282110.       2829885.5       10282181.
        2829819.       10282131.      2830063.75       10281744.
      2830183.75       10281649.       2831166.5       10281843.

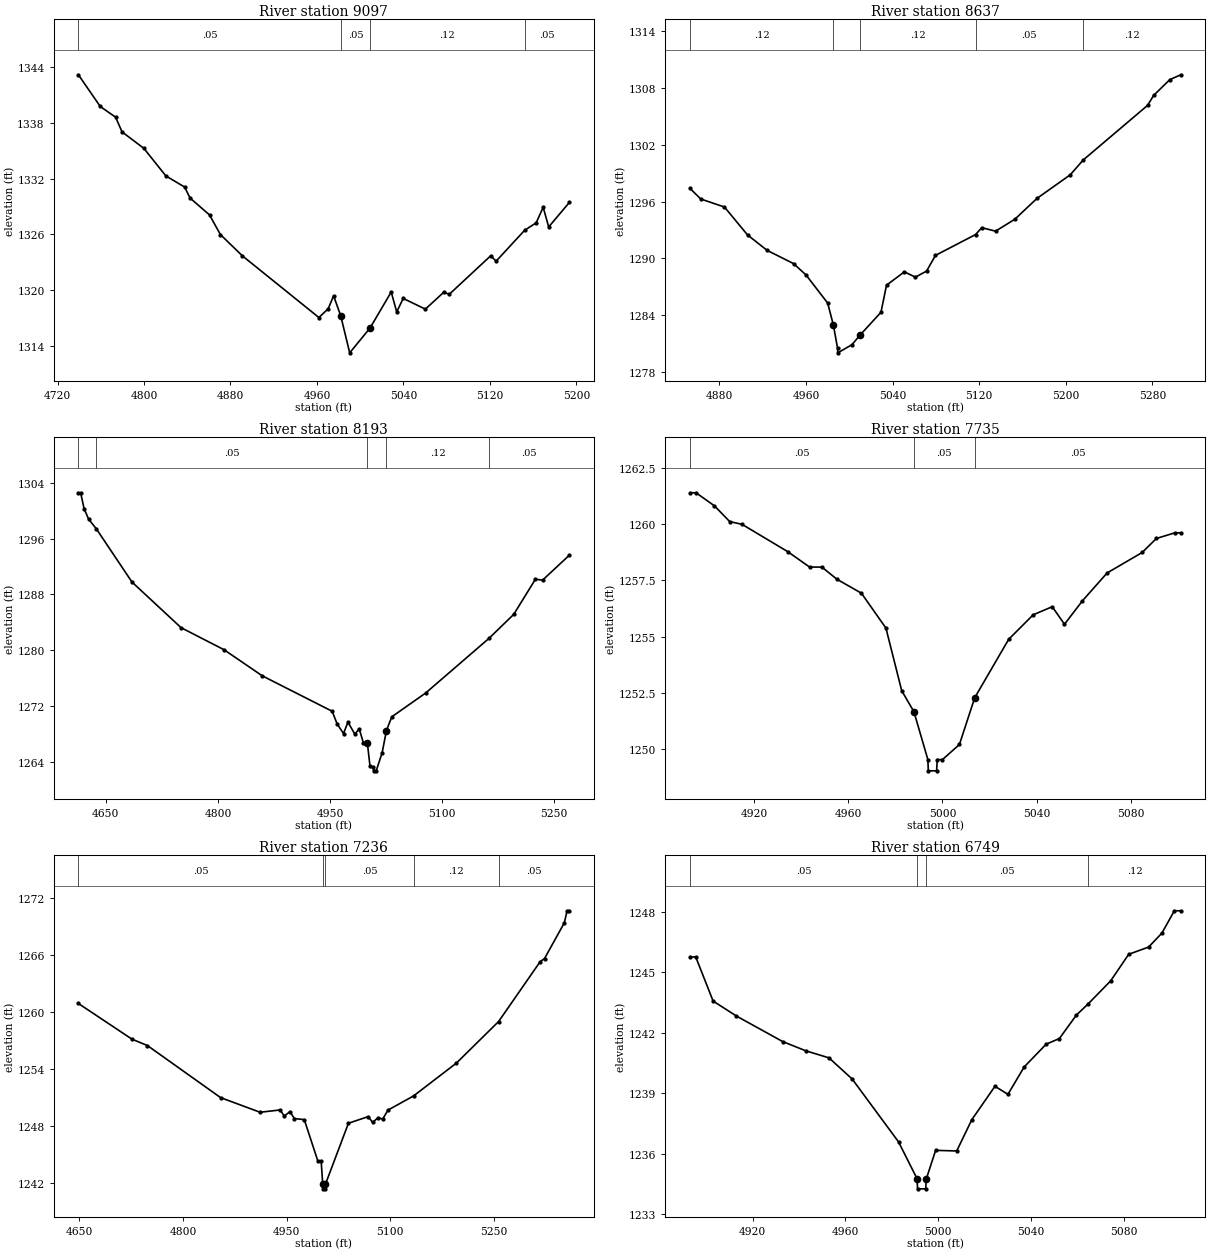
Type RM Length L Ch R = 1 ,9097    ,460,460,460
BEGIN DESCRIPTION:
LITTLE LLANO 057 20.0
END DESCRIPTION:
XS GIS Cut Line= 3
      2824505.72     10282403.12       2824763.5       10282442.
      2824805.68     10282253.15
#Sta/Elev= 30
  4739.3 1343.14  4759.5 1339.74  4773.7 1338.59  4779.7 1337.01  4799.9 1335.24
  4820.2 1332.29  4837.6 1331.09  4842.6 1329.91  4860.6  1328.1  4870.7 1325.99
    4891 1323.71  4961.8 1317.09  4970.4 1318.03  4975.4 1319.42    4982 1317.27
  4990.3  1313.3  5009.1 1315.96  5028.7 1319.83  5033.8 1317.69  5039.8 1319.14
  5060.3 1317.99  5077.3  1319.8  5082.4 1319.58  5120.7 1323.71  5125.8 1323.14
  5152.2 1326.46  5162.8 1327.25  5169.3 1328.92  5174.4 1326.81  5193.5 1329.44
#Mann= 4 ,-1 , 0
  4739.3     .05       0    4982     .05       0  5009.1     .12       0
  5152.2     .05       0
Bank Sta=4982,5009.1
XS Rating Curve= 0 ,0
Exp/Cntr=0.3,0.1

Type RM Length L Ch R = 1 ,8637    ,444,444,444
BEGIN DESCRIPTION:
LITTLE LLANO 057 19.0
END DESCRIPTION:
XS GIS Cut Line= 3
       2824905.7     10282853.11        2825044.       10282803.
      2825105.69     10282503.08
#Sta/Elev= 30
  4852.9  1297.4  4862.9 1296.27  4884.8 1295.42  4906.1 1292.47  4924.2 1290.84
  4948.6 1289.44  4960.1 1288.24  4980.1 1285.27  4985.4 1282.92  4989.2 1280.51
  4989.4 1280.01  5002.5 1280.87  5010.1  1281.9  5029.3  1284.3  5034.4 1287.16
  5050.9 1288.57  5061.1 1288.01  5071.4 1288.65  5079.6 1290.31  5116.6 1292.51
  5122.4 1293.24  5135.1 1292.87    5153 1294.14  5173.4 1296.34  5204.1 1298.83
    5216 1300.39  5275.5 1306.17    5281 1307.21    5296 1308.89  5306.2  1309.4
#Mann= 5 ,-1 , 0
  4852.9     .12       0  4985.4     .05       0  5010.1     .12       0
  5116.6     .05       0    5216     .12       0
Bank Sta=4985.4,5010.1
XS Rating Curve= 0 ,0
Exp/Cntr=0.3,0.1

Type RM Length L Ch R = 1 ,8193    ,458,458,458
BEGIN DESCRIPTION:
LITTLE LLANO 057 18.0
END DESCRIPTION:
XS GIS Cut Line= 3
      2825005.65     10283353.14       2825329.5       10283142.
       2825455.7     10282903.08
#Sta/Elev= 30
  4613.4 1302.56  4616.4 1302.56    4621 1300.29    4627  1298.8  4637.4 1297.39
  4685.1 1289.76  4750.8 1283.22  4808.1 1280.07  4859.4 1276.32  4952.9 1271.24
  4959.6 1269.41  4968.1 1268.05    4974 1269.68  4983.2 1267.96  4989.1 1268.71
  4994.7  1266.7    5000  1266.7  5003.5 1263.37  5008.1  1263.2  5008.3  1262.7
  5011.8  1262.7  5019.8 1265.31  5025.5 1268.48  5032.7 1270.45  5077.9 1273.85
  5162.8  1281.7  5195.9 1285.14  5224.9 1290.18  5234.3 1290.03  5270.2 1293.61
#Mann= 5 ,-1 , 0
  4613.4     .12       0  4637.4     .05       0    5000     .05       0
  5025.5     .12       0  5162.8     .05       0
Bank Sta=5000,5025.5
XS Rating Curve= 0 ,0
Exp/Cntr=0.3,0.1

Type RM Length L Ch R = 1 ,7735    ,499,499,499
BEGIN DESCRIPTION:
LITTLE LLANO 057 17.0
END DESCRIPTION:
XS GIS Cut Line= 3
      2825655.68     10283503.11        2825685.       10283400.
      2825655.69     10283303.14
#Sta/Elev= 30
  4892.8 1261.39  4895.4 1261.39  4903.2 1260.81  4909.7 1260.11  4914.9 1259.99
  4934.4 1258.77  4943.6 1258.09  4948.8 1258.09  4955.2 1257.55  4965.6 1256.93
    4976 1255.38  4982.7  1252.6  4987.9 1251.66  4993.8 1249.54    4994 1249.04
  4997.5 1249.04  4997.8 1249.54    5000 1249.54  5007.2 1250.21  5013.7 1252.29
  5028.1 1254.88  5038.5 1255.97  5046.6 1256.33  5051.8 1255.55  5059.4 1256.59
  5069.9 1257.83  5084.8 1258.74  5090.8 1259.36  5098.6 1259.61  5101.2 1259.61
#Mann= 3 , 0 , 0
  4892.8     .05       0  4987.9     .05       0  5013.7     .05       0
Bank Sta=4987.9,5013.7
XS Rating Curve= 0 ,0
Exp/Cntr=0.3,0.1

Type RM Length L Ch R = 1 ,7236    ,487,487,487
BEGIN DESCRIPTION:
LITTLE LLANO 057 16.0
END DESCRIPTION:
XS GIS Cut Line= 3
      2825855.66     10283603.14      2826076.75       10283330.
       2826305.7     10283053.09
#Sta/Elev= 30
  4648.6 1260.87  4726.2 1257.11  4748.5 1256.44  4854.5 1250.95  4911.6 1249.41
  4940.4 1249.65  4946.8 1249.01  4954.8 1249.48  4961.2 1248.75  4975.6 1248.63
  4995.2 1244.28    5000 1244.28  5002.3 1241.84  5002.6 1241.34  5006.1 1241.34
  5006.3 1241.84  5039.5 1248.25  5068.1 1248.95  5074.6 1248.34  5082.5 1248.85
    5089 1248.68  5096.8 1249.64  5133.8 1251.13  5195.8 1254.59  5256.9 1258.97
    5317 1265.27  5323.4 1265.61  5352.1 1269.38    5356 1270.64  5359.3 1270.64
#Mann= 5 ,-1 , 0
  4648.6     .05       0  5002.3     .05       0  5006.3     .05       0
  5133.8     .12       0  5256.9     .05       0
Bank Sta=5002.3,5006.3
XS Rating Curve= 0 ,0
Exp/Cntr=0.3,0.1

Type RM Length L Ch R = 1 ,6749    ,411,411,411
BEGIN DESCRIPTION:
LITTLE LLANO 057 15.0
END DESCRIPTION:
XS GIS Cut Line= 3
      2826505.68     10283503.09        2826504.       10283396.
      2826455.69     10283303.11
#Sta/Elev= 29
  4892.9 1245.77  4895.4 1245.77  4902.9 1243.58  4912.9 1242.84  4932.9 1241.57
  4942.9 1241.11  4952.9 1240.76  4962.9 1239.71  4982.9 1236.59  4990.9 1234.76
  4991.1 1234.26  4994.6 1234.26  4994.9 1234.76  4998.9 1236.17    5008 1236.14
  5014.5 1237.69  5024.5 1239.35  5030.1 1238.95  5037.1 1240.31  5046.6 1241.44
  5052.3 1241.72  5059.6 1242.88  5064.8 1243.45  5074.4 1244.58  5082.2  1245.9
  5090.8 1246.26  5096.5 1246.95  5101.9 1248.06  5104.7 1248.06
#Mann= 4 ,-1 , 0
  4892.9     .05       0  4990.9     .03       0  4994.9     .05       0
  5064.8     .12       0
Bank Sta=4990.9,4994.9
XS Rating Curve= 0 ,0
Exp/Cntr=0.3,0.1

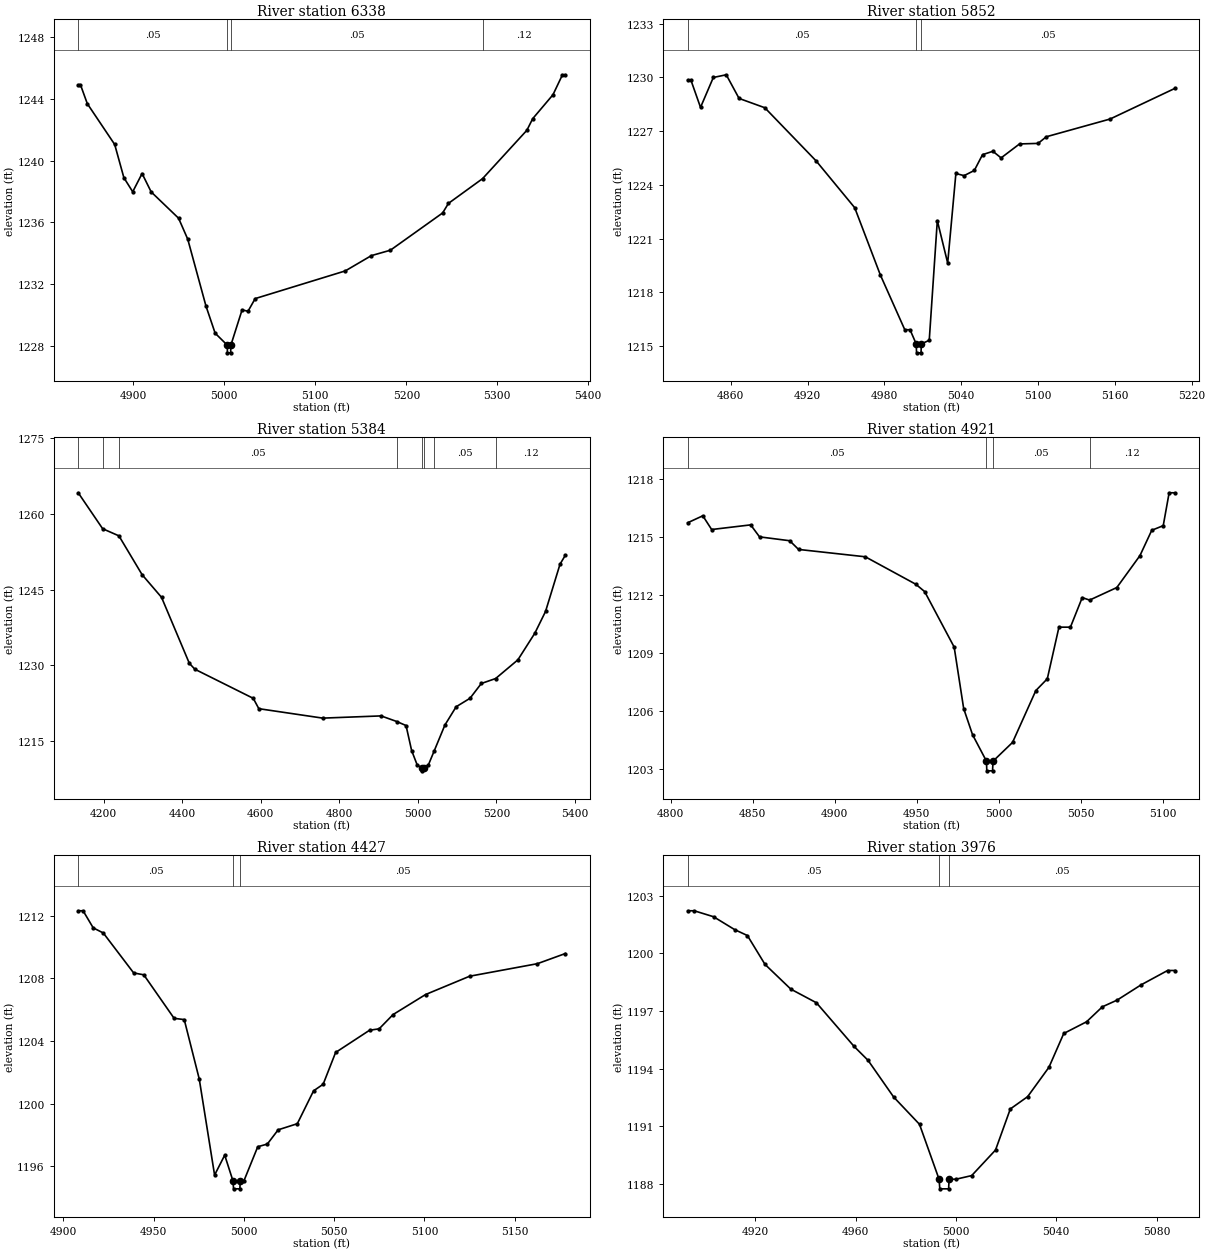
Type RM Length L Ch R = 1 ,6338    ,486,486,486
BEGIN DESCRIPTION:
LITTLE LLANO 057 14.0
END DESCRIPTION:
XS GIS Cut Line= 3
      2826905.68     10283653.12      2826893.25       10283493.
      2826655.68     10283203.11
#Sta/Elev= 30
  4839.4  1244.9  4841.9  1244.9  4849.4 1243.68  4879.5 1241.04  4889.6 1238.89
  4899.3 1237.98  4909.6 1239.16  4919.6 1237.97  4949.7 1236.27  4959.8 1234.91
  4979.8 1230.59  4989.9 1228.83  5003.2 1228.06  5003.4 1227.56  5006.9 1227.56
  5007.2 1228.06  5019.5 1230.34    5026 1230.25  5033.9 1231.07  5132.9 1232.86
  5161.6 1233.85  5182.5  1234.2  5239.9 1236.61  5246.3 1237.23  5283.8 1238.83
  5332.5 1241.96  5338.9 1242.71  5361.2 1244.26  5371.6 1245.55  5374.8 1245.55
#Mann= 4 ,-1 , 0
  4839.4     .05       0  5003.2     .03       0  5007.2     .05       0
  5283.8     .12       0
Bank Sta=5003.2,5007.2
XS Rating Curve= 0 ,0
Exp/Cntr=0.3,0.1

Type RM Length L Ch R = 1 ,5852    ,468,468,468
BEGIN DESCRIPTION:
LITTLE LLANO 057 13.0
END DESCRIPTION:
XS GIS Cut Line= 3
      2827305.69     10283503.09        2827319.       10283330.
       2827155.7     10283203.12
#Sta/Elev= 30
  4826.4 1229.85  4828.9 1229.85  4836.4 1228.33  4846.4    1230  4856.5 1230.15
  4866.5 1228.83  4886.6 1228.31  4926.7 1225.34  4956.8 1222.73  4976.8 1218.98
  4995.9 1215.92    5000 1215.92  5004.8 1215.13  5005.1 1214.63  5008.6 1214.63
  5008.8 1215.13    5015 1215.33  5021.3 1222.01  5029.4 1219.64  5035.8 1224.64
  5042.2 1224.52  5050.2 1224.81  5056.6 1225.69  5064.7 1225.88  5071.1 1225.51
  5085.5 1226.29    5100 1226.32  5106.4 1226.69  5156.2 1227.68  5206.8 1229.39
#Mann= 3 ,-1 , 0
  4826.4     .05       0  5004.8     .03       0  5008.8     .05       0
Bank Sta=5004.8,5008.8
XS Rating Curve= 0 ,0
Exp/Cntr=0.3,0.1

Type RM Length L Ch R = 1 ,5384    ,463,463,463
BEGIN DESCRIPTION:
LITTLE LLANO 057 12.0
END DESCRIPTION:
XS GIS Cut Line= 3
      2828255.68     10283653.11      2827639.25       10283047.
      2827405.68     10282753.11
#Sta/Elev= 30
  4135.5 1264.17  4197.7 1257.05  4239.1 1255.64  4298.2 1247.94  4347.6 1243.46
  4418.3  1230.4  4432.5 1229.22    4581 1223.46  4595.2 1221.41  4757.8 1219.54
  4906.3 1219.98  4946.2 1218.87  4969.9 1218.07  4984.1 1213.12  4998.2 1210.28
  5010.6  1209.6  5010.8  1209.1  5014.6  1209.6    5027 1210.32  5041.3    1213
  5068.8 1218.17  5097.4 1221.79  5132.7 1223.47  5161.5  1226.4  5197.9 1227.38
  5254.5 1231.08  5297.7 1236.36  5324.9 1240.66  5361.8 1250.03  5375.4 1251.81
#Mann= 8 ,-1 , 0
  4135.5     .05       0  4197.7     .12       0  4239.1     .05       0
  4946.2     .12       0  5010.6     .07       0  5014.6     .12       0
  5041.3     .05       0  5197.9     .12       0
Bank Sta=5010.6,5014.6
XS Rating Curve= 0 ,0
Exp/Cntr=0.3,0.1

Type RM Length L Ch R = 1 ,4921    ,494,494,494
BEGIN DESCRIPTION:
LITTLE LLANO 057 11.0
END DESCRIPTION:
XS GIS Cut Line= 3
       2827905.7     10283003.07      2827978.75       10282828.
      2828055.71     10282753.09
#Sta/Elev= 30
  4810.3 1215.75  4819.5 1216.11  4824.9  1215.4  4848.7 1215.64  4854.1 1215.02
  4872.5 1214.82  4877.9 1214.37  4918.6 1213.99  4949.4 1212.57  4954.8 1212.19
  4972.8 1209.32  4978.6 1206.14    4984 1204.79  4992.5 1203.42  4992.7 1202.92
  4996.2 1202.92  4996.5 1203.42  5008.4 1204.39  5022.6 1207.07  5029.6 1207.68
  5036.7 1210.35  5043.7 1210.35  5050.9 1211.88  5055.4 1211.75    5072  1212.4
  5086.1 1214.05  5093.3 1215.36  5100.3  1215.6  5103.9  1217.3  5107.4  1217.3
#Mann= 4 ,-1 , 0
  4810.3     .05       0  4992.5     .03       0  4996.5     .05       0
  5055.4     .12       0
Bank Sta=4992.5,4996.5
XS Rating Curve= 0 ,0
Exp/Cntr=0.3,0.1

Type RM Length L Ch R = 1 ,4427    ,451,451,451
BEGIN DESCRIPTION:
LITTLE LLANO 057 10.0
END DESCRIPTION:
XS GIS Cut Line= 3
      2828405.66     10283153.07      2828364.75       10283071.
      2828305.68     10282903.09
#Sta/Elev= 30
  4908.3 1212.31    4911 1212.31  4916.6 1211.22  4922.2 1210.89    4939 1208.34
  4944.6 1208.22  4961.4 1205.44    4967 1205.36  4975.3 1201.57  4983.8 1195.43
  4989.4  1196.7    4994 1195.05  4994.3 1194.55  4997.8 1194.55    4998 1195.05
    5000 1195.05  5007.7 1197.24    5013 1197.41    5019 1198.32  5029.6 1198.71
  5038.6 1200.81  5043.9 1201.23  5050.8 1203.26  5069.6 1204.68  5074.9 1204.77
  5082.6 1205.68  5100.6 1206.96    5125 1208.13  5162.5 1208.93    5178 1209.58
#Mann= 3 ,-1 , 0
  4908.3     .05       0    4994     .03       0    4998     .05       0
Bank Sta=4994,4998
XS Rating Curve= 0 ,0
Exp/Cntr=0.3,0.1

Type RM Length L Ch R = 1 ,3976    ,354,354,354
BEGIN DESCRIPTION:
LITTLE LLANO 057 9.0
END DESCRIPTION:
XS GIS Cut Line= 3
      2828755.69      10283003.1        2828780.       10282899.
      2828705.72     10282853.13
#Sta/Elev= 29
  4893.1 1202.22  4895.7 1202.22  4903.4 1201.91  4911.8 1201.24  4916.9 1200.93
  4923.9 1199.43  4934.2 1198.14  4944.4 1197.43  4959.4 1195.16    4965 1194.43
  4975.2 1192.52  4985.5  1191.1  4993.3 1188.24  4993.6 1187.74  4997.1 1187.74
  4997.3 1188.24    5000 1188.24  5006.3 1188.43  5015.8 1189.76  5021.7  1191.9
  5028.6 1192.54  5037.1 1194.07    5043 1195.83  5052.1 1196.44  5058.4 1197.22
  5064.3 1197.57  5073.8 1198.36  5084.4 1199.11  5087.3 1199.11
#Mann= 3 ,-1 , 0
  4893.1     .05       0  4993.3     .03       0  4997.3     .05       0
Bank Sta=4993.3,4997.3
XS Rating Curve= 0 ,0
Exp/Cntr=0.3,0.1

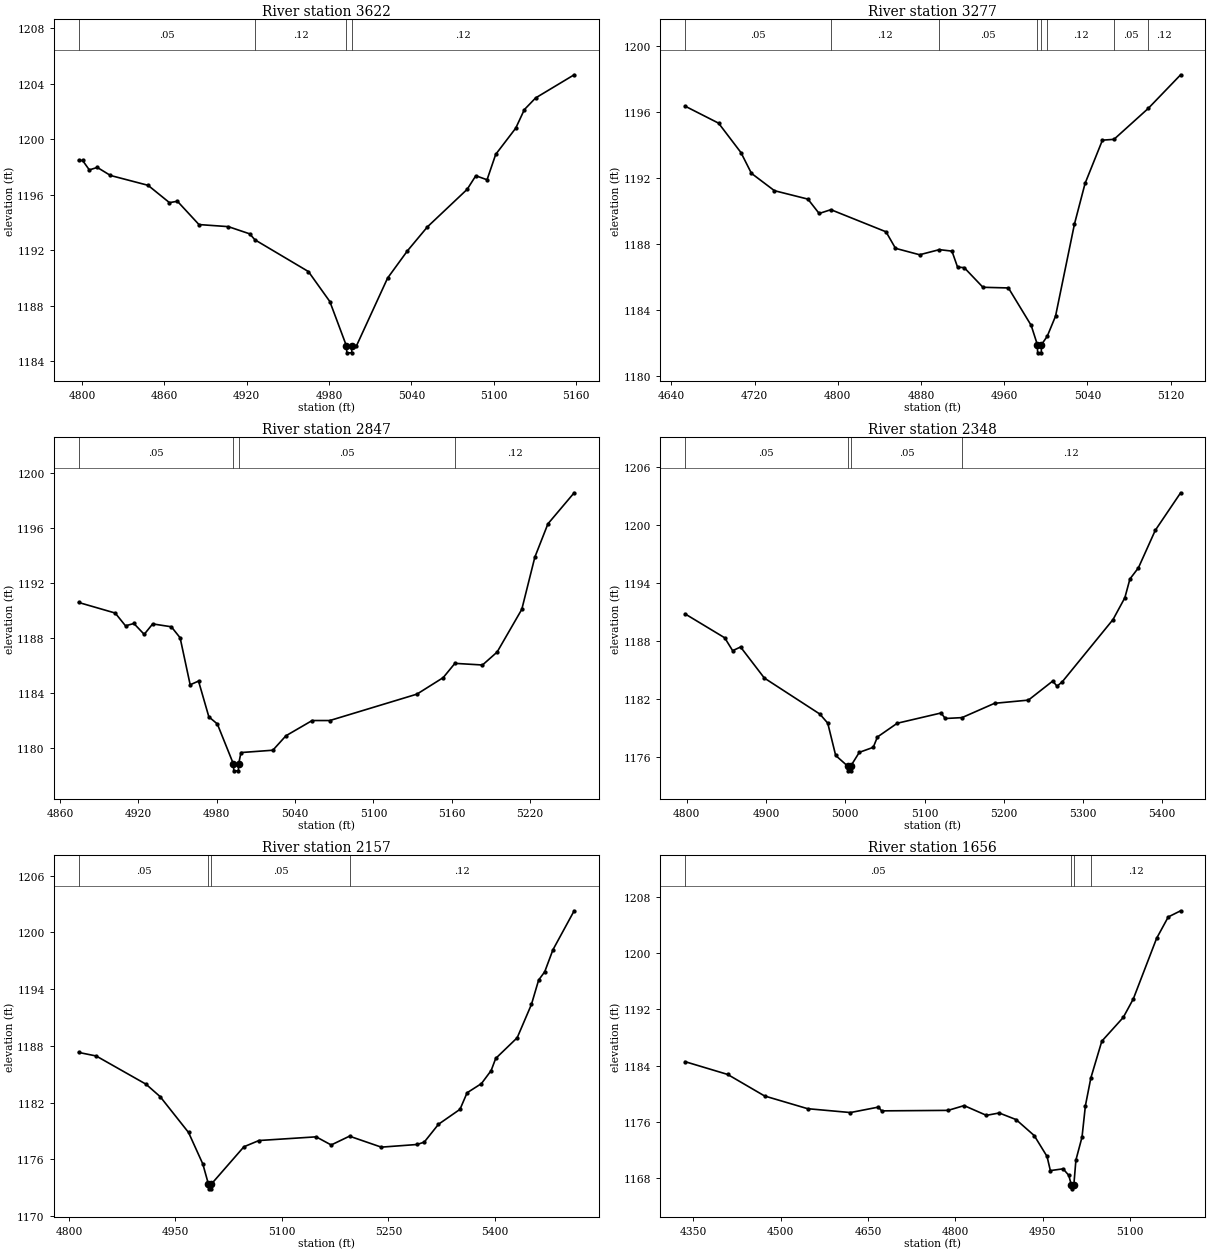
Type RM Length L Ch R = 1 ,3622    ,345,345,345
BEGIN DESCRIPTION:
LITTLE LLANO 057 8.0
END DESCRIPTION:
XS GIS Cut Line= 3
      2829155.68      10282853.1      2829052.25       10282679.
      2828955.66     10282553.08
#Sta/Elev= 30
  4797.5 1198.46  4800.4 1198.46  4805.3 1197.78  4811.1 1197.96  4820.7 1197.38
  4848.1 1196.67  4863.7 1195.42  4869.5 1195.52  4885.2 1193.84  4906.6 1193.69
  4922.2 1193.17    4926 1192.74    4965 1190.45  4980.6 1188.29  4992.7 1185.09
    4993 1184.59  4996.5 1184.59  4996.7 1185.09    5000 1185.09  5022.7 1189.98
  5037.2 1191.95  5051.7 1193.67  5080.7 1196.38    5087 1197.36  5095.2 1197.07
  5101.5  1198.9  5116.1 1200.79  5122.4 1202.13  5130.6 1202.97  5158.7 1204.64
#Mann= 4 ,-1 , 0
  4797.5     .05       0    4926     .12       0  4992.7     .07       0
  4996.7     .12       0
Bank Sta=4992.7,4996.7
XS Rating Curve= 0 ,0
Exp/Cntr=0.3,0.1

Type RM Length L Ch R = 1 ,3277    ,430,430,430
BEGIN DESCRIPTION:
LITTLE LLANO 057 7.0
END DESCRIPTION:
XS GIS Cut Line= 3
      2829205.69     10282803.09        2829332.       10282480.
      2829305.68      10282353.1
#Sta/Elev= 30
  4653.1 1196.36  4685.3 1195.33  4706.8 1193.55  4716.9 1192.29    4739 1191.24
  4771.2 1190.73    4782 1189.86  4793.3 1190.09  4846.3 1188.75  4855.4 1187.75
  4878.6 1187.36  4897.6 1187.67  4909.7 1187.58  4915.1 1186.61  4921.5 1186.58
  4939.5 1185.39    4964 1185.35  4985.9 1183.08  4991.8 1181.92  4992.1 1181.42
  4995.6 1181.42  4995.8 1181.92  5001.3 1182.42  5009.3 1183.64  5027.5 1189.22
  5037.7 1191.68  5054.4  1194.3  5065.5 1194.35  5098.4 1196.22  5129.6 1198.26
#Mann= 8 ,-1 , 0
  4653.1     .05       0  4793.3     .12       0  4897.6     .05       0
  4991.8     .03       0  4995.8     .05       0  5001.3     .12       0
  5065.5     .05       0  5098.4     .12       0
Bank Sta=4991.8,4995.8
XS Rating Curve= 0 ,0
Exp/Cntr=0.3,0.1

Type RM Length L Ch R = 1 ,2847    ,499,499,499
BEGIN DESCRIPTION:
LITTLE LLANO 057 6.0
END DESCRIPTION:
XS GIS Cut Line= 3
      2829555.69     10282653.11       2829635.5       10282556.
      2829655.68      10282303.1
#Sta/Elev= 30
  4874.3 1190.61  4902.3 1189.84  4910.2 1188.91  4916.6 1189.08  4924.5 1188.29
    4931 1189.05  4945.3 1188.84    4952 1188.04  4959.7 1184.62  4966.1 1184.89
    4974 1182.29  4980.5 1181.77  4992.8 1178.86  4993.1 1178.36  4996.6 1178.36
  4996.8 1178.86  4998.6 1179.69    5023 1179.86    5033 1180.91  5053.1 1182.02
  5066.6 1182.02  5133.3 1183.94  5153.4 1185.14  5162.4 1186.18  5183.5 1186.06
  5194.7    1187  5213.6 1190.11  5223.6 1193.91  5233.6 1196.33  5253.7 1198.59
#Mann= 4 ,-1 , 0
  4874.3     .05       0  4992.8     .03       0  4996.8     .05       0
  5162.4     .12       0
Bank Sta=4992.8,4996.8
XS Rating Curve= 0 ,0
Exp/Cntr=0.3,0.1

Type RM Length L Ch R = 1 ,2348    ,191,191,191
BEGIN DESCRIPTION:
LITTLE LLANO 057 5.0
END DESCRIPTION:
XS GIS Cut Line= 3
      2830055.68     10282603.07      2830052.25       10282401.
      2829655.73     10282253.13
#Sta/Elev= 30
  4797.9 1190.84  4847.9 1188.37  4857.9 1187.04  4867.9 1187.42  4897.9 1184.21
  4967.9 1180.49  4977.9 1179.55  4987.9 1176.21  5002.9 1175.12  5003.2 1174.62
  5006.8 1174.62    5007 1175.12  5017.7 1176.53  5035.3 1177.05  5040.6 1178.12
  5065.6 1179.54  5120.9  1180.6  5126.2 1180.03  5147.3 1180.12  5188.4  1181.6
  5231.1 1181.93  5261.8  1183.9  5267.2 1183.37  5273.8 1183.82  5337.9 1190.26
  5352.8 1192.51  5359.2 1194.45  5369.9  1195.6  5391.2 1199.48  5423.2 1203.36
#Mann= 4 ,-1 , 0
  4797.9     .05       0  5002.9     .03       0    5007     .05       0
  5147.3     .12       0
Bank Sta=5002.9,5007
XS Rating Curve= 0 ,0
Exp/Cntr=0.3,0.1

Type RM Length L Ch R = 1 ,2157    ,501,501,501
BEGIN DESCRIPTION:
LITTLE LLANO 057 4.0
END DESCRIPTION:
XS GIS Cut Line= 3
      2830370.45     10282301.75      2830134.99      10282290.9
      2829675.99     10282233.39
#Sta/Elev= 30
  4813.6 1187.31  4838.4 1186.93  4908.5 1183.95  4928.5 1182.63  4968.5 1178.84
  4988.6 1175.51  4996.5 1173.38  4996.8 1172.88  5000.4 1172.88  5000.6 1173.38
  5046.5 1177.33  5067.7 1177.99  5148.3 1178.38  5169.5 1177.52  5195.3 1178.45
  5240.1 1177.29  5290.5 1177.57  5300.6 1177.82  5320.7 1179.71    5351 1181.29
    5361 1183.04  5381.2 1184.01  5394.9 1185.39  5401.3 1186.67  5431.6 1188.86
  5451.7 1192.39  5461.8 1194.96  5470.4 1195.84    5482 1198.17  5511.9 1202.29
#Mann= 4 ,-1 , 0
  4813.6     .05       0  4996.5     .05       0  5000.6     .05       0
  5195.3     .12       0
Bank Sta=4996.5,5000.6
XS Rating Curve= 0 ,0
Exp/Cntr=0.3,0.1

Type RM Length L Ch R = 1 ,1656    ,201,201,201
BEGIN DESCRIPTION:
Mapping XS a3dc6d12
END DESCRIPTION:
XS GIS Cut Line= 4
      2830445.33     10282172.63      2830048.18     10282041.33
      2829755.21     10282197.58      2829654.34      10282196.5
#Sta/Elev= 30
  4335.7 1184.56  4408.8 1182.74  4472.3 1179.67  4546.2 1177.86  4619.7 1177.31
  4667.9 1178.09  4673.2 1177.55  4787.4 1177.62    4815  1178.3  4853.3 1176.91
  4875.2 1177.25  4904.2 1176.31  4935.4 1174.03  4957.4 1171.06  4963.1 1169.04
    4985 1169.29  4994.8 1168.36  4999.3 1166.94  4999.5 1166.44  5003.4 1166.94
    5007 1170.54  5017.5 1173.81  5023.3 1178.28  5032.7 1182.25  5051.5 1187.48
  5088.3 1190.86  5105.6  1193.5  5145.6 1202.13  5165.6 1205.18  5186.9 1206.06
#Mann= 4 ,-1 , 0
  4335.7     .05       0  4999.3     .05       0  5003.4     .05       0
  5032.7     .12       0
Bank Sta=4999.3,5003.4
XS Rating Curve= 0 ,0
Exp/Cntr=0.3,0.1

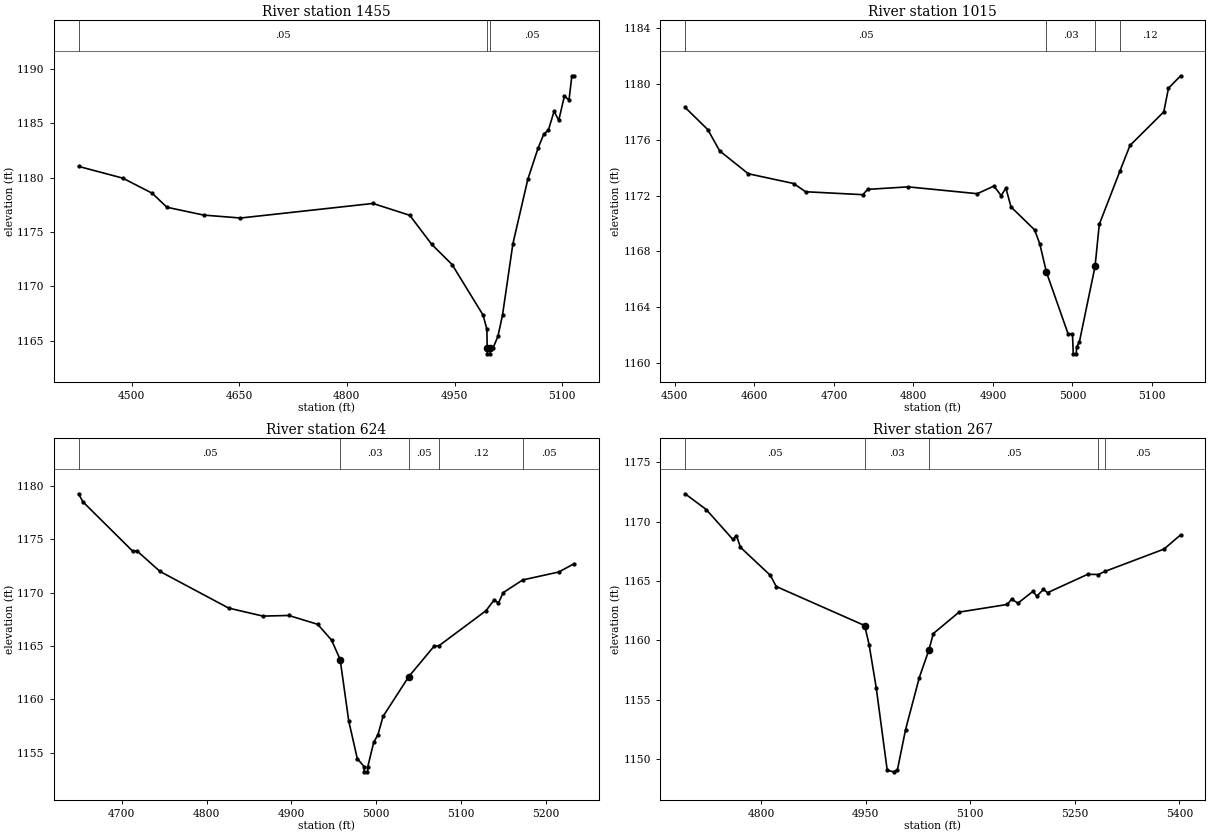
Type RM Length L Ch R = 1 ,1455    ,440,440,440
BEGIN DESCRIPTION:
LITTLE LLANO 057 3.0
END DESCRIPTION:
XS GIS Cut Line= 3
      2830455.67     10282103.11        2829896.       10281977.
      2829805.68      10281903.1
#Sta/Elev= 30
  4426.3 1181.04  4487.8 1179.96  4528.8 1178.57  4549.3 1177.28  4600.5 1176.56
  4651.8 1176.29  4836.3 1177.63  4887.6 1176.54  4918.3 1173.86  4946.7    1172
  4989.9 1167.34  4995.1 1166.04  4995.5 1164.29  4995.8 1163.79  4999.4 1163.79
  4999.6 1164.29  5003.4 1164.29  5010.5  1165.4  5016.9 1167.38  5031.3 1173.91
  5052.1 1179.85  5066.4 1182.72  5074.3    1184  5080.8 1184.39  5088.7 1186.11
  5095.2 1185.28  5103.1 1187.51  5109.5 1187.15  5113.5 1189.38  5116.7 1189.38
#Mann= 3 ,-1 , 0
  4426.3     .05       0  4995.5     .05       0  4999.6     .05       0
Bank Sta=4995.5,4999.6
XS Rating Curve= 0 ,0
Exp/Cntr=0.3,0.1

Type RM Length L Ch R = 1 ,1015    ,391,391,391
BEGIN DESCRIPTION:
LITTLE LLANO 057 2.0
END DESCRIPTION:
XS GIS Cut Line= 3
      2830455.69     10282053.12      2830183.75       10281649.
      2830055.72     10281603.12
#Sta/Elev= 30
  4512.9 1178.33  4541.4 1176.74  4556.4 1175.21  4592.4 1173.57  4649.4 1172.87
  4664.4 1172.28  4736.4 1172.07  4742.4 1172.45  4793.4 1172.63  4880.3 1172.14
  4901.3 1172.69  4910.3    1172  4916.3 1172.54  4922.7 1171.19  4952.3 1169.55
  4958.9 1168.54  4967.3  1166.5  4994.5 1162.08    5000 1162.08    5001 1160.65
  5004.8 1160.65  5005.1 1161.15  5008.6 1161.48  5028.4 1166.93  5033.7 1169.94
  5059.9  1173.8  5072.3  1175.6  5114.8 1178.01  5120.7 1179.71    5136  1180.6
#Mann= 4 ,-1 , 0
  4512.9     .05       0  4967.3     .03       0  5028.4     .05       0
  5059.9     .12       0
Bank Sta=4967.3,5028.4
XS Rating Curve= 0 ,0
Exp/Cntr=0.3,0.1

Type RM Length L Ch R = 1 ,624     ,357,357,357
BEGIN DESCRIPTION:
Mapping XS 964d28a9
END DESCRIPTION:
XS GIS Cut Line= 2
      2830511.32     10282068.11      2830593.27     10281490.29
#Sta/Elev= 30
  4649.4 1179.25  4654.4  1178.5  4713.1 1173.87  4718.1  1173.9  4745.3 1171.97
  4826.1 1168.54  4866.5 1167.79  4896.8 1167.85    4931 1167.02  4947.3 1165.54
  4957.4 1163.72  4967.5 1157.97  4977.6 1154.43  4985.5  1153.7  4985.8  1153.2
  4989.6  1153.2    4990  1153.7  4996.9 1155.96  5001.9 1156.68  5007.9 1158.39
  5038.2 1162.12  5067.8 1164.95  5073.9 1165.02  5129.2  1168.3  5138.8 1169.31
  5143.8 1169.01  5149.4 1169.99  5172.5 1171.18  5214.8 1171.92    5233  1172.7
#Mann= 5 ,-1 , 0
  4649.4     .05       0  4957.4     .03       0  5038.2     .05       0
  5073.9     .12       0  5172.5     .05       0
Bank Sta=4957.4,5038.2
XS Rating Curve= 0 ,0
Exp/Cntr=0.3,0.1

Type RM Length L Ch R = 1 ,267     ,0,0,0
BEGIN DESCRIPTION:
LITTLE LLANO 057 1.0
END DESCRIPTION:
XS GIS Cut Line= 3
       2830844.7     10282080.61      2830936.38     10281670.84
      2830690.56      10281515.3
#Sta/Elev= 30
  4691.1 1172.34  4721.5 1171.01  4759.7 1168.49  4764.8 1168.82  4770.5 1167.83
  4813.4 1165.47  4821.8 1164.53  4948.7 1161.24    4955 1159.64  4965.2 1156.02
 4981.02 1149.06  4990.1 1148.92 4995.74 1149.11 5007.31 1152.47 5027.04 1156.86
  5040.6 1159.15  5047.2 1160.57    5084 1162.37  5153.4 1163.02  5159.3 1163.46
  5168.6 1163.13  5189.8 1164.11  5195.7 1163.72  5205.1 1164.29    5211 1164.01
  5268.7 1165.56  5283.8 1165.54  5293.3  1165.8    5378 1167.68  5401.9 1168.88
#Mann= 5 ,-1 , 0
  4691.1     .05       0  4948.7     .03       0  5040.6     .05       0
  5283.8     .12       0  5293.3     .05       0
Bank Sta=4948.7,5040.6
XS Rating Curve= 0 ,0
Exp/Cntr=0.3,0.1

Chan Stop Cuts=-1
Use User Specified Reach Order=0
Composite Channel Slope=5