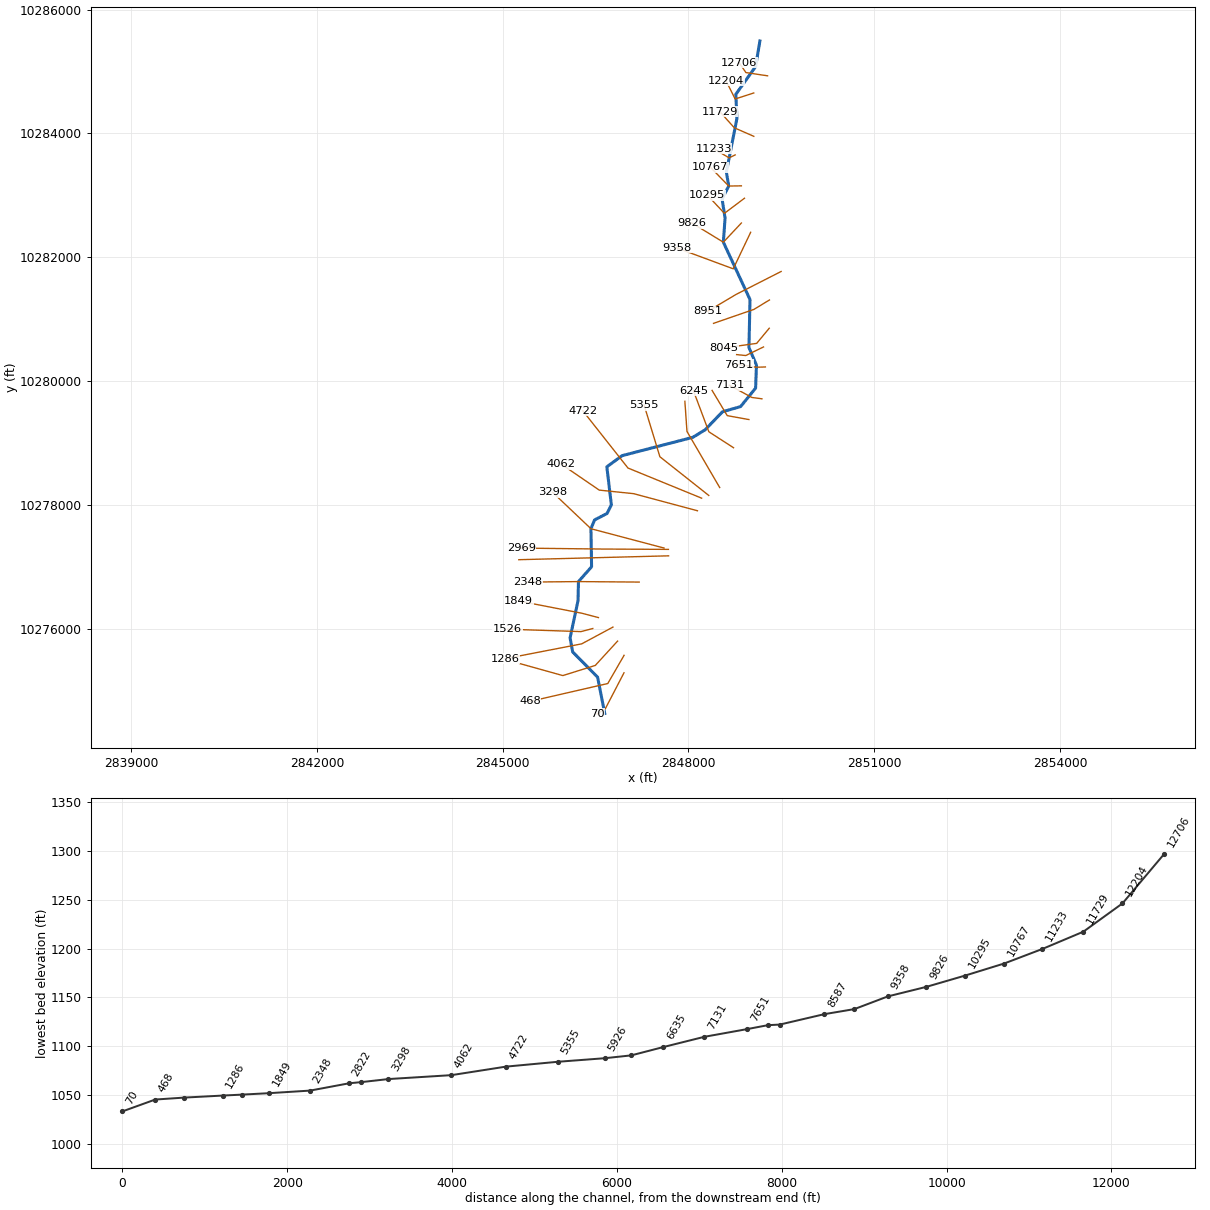
--- LITTLE LLANO 058.prj (project) ---

Proj Title=LITTLE LLANO 058 Base Level Engineering
Current Plan=p01
Default Exp/Contr=0.3,0.1
English Units
Geom File=g01
Flow File=f01
Plan File=p01
Y Axis Title=Elevation
X Axis Title(PF)=Main Channel Distance
X Axis Title(XS)=Station
BEGIN DESCRIPTION:
LITTLE LLANO 058
END DESCRIPTION:
DSS Export Rating Curves= 0
DSS Export Rating Curve Sorted= 0
DSS Export Volume Flow Curves= 0
DXF OffsetX= 0
DXF OffsetY= 0
DXF ScaleX= 1
DXF ScaleY= 10

--- LITTLE LLANO 058.p01 (plan) ---

Plan Title=Multiple Run
Short Identifier=Multiple
Geom File=g01
Flow File=f01
Subcritical Flow
K Sum by GR= 0
Std Step Tol= 0.01
Critical Tol= 0.01
Num of Std Step Trials= 20
Max Error Tol= 0.3
Flow Tol Ratio= 0.001
Split Flow NTrial= 30
Split Flow Tol= 0.02
Split Flow Ratio= 0.02
Log Output Level= 0
Friction Slope Method= 1
Unsteady Friction Slope Method= 2
Unsteady Bridges Friction Slope Method= 1
Parabolic Critical Depth
Global Vel Dist=  1 , 1 , 1
Global Log Level= 0
CheckData=True
Encroach Param= -1, 0, 0, 0
BEGIN DESCRIPTION:
Multiple Run
END DESCRIPTION:

--- LITTLE LLANO 058.f01 (steady flow) ---

Flow Title=Multiple
Program Version=4.10
Number of Profiles= 7
Profile Names=10-year,25-year,50-year,1pct_min,100-year,1pct_plu,500-year
River Rch & RM=LITTLE LLANO 058,Reach-1         ,12706
     535     884    2034    1565    2934    5501    4369
River Rch & RM=LITTLE LLANO 058,Reach-1         ,2348
     628    1050    2357    1772    3407    6552    5054
Boundary for River Rch & Prof#=LITTLE LLANO 058,Reach-1         , 1
Up Type= 0
Dn Type= 3
Dn Slope=0.02
Boundary for River Rch & Prof#=LITTLE LLANO 058,Reach-1         , 2
Up Type= 0
Dn Type= 3
Dn Slope=0.02
Boundary for River Rch & Prof#=LITTLE LLANO 058,Reach-1         , 3
Up Type= 0
Dn Type= 3
Dn Slope=0.02
Boundary for River Rch & Prof#=LITTLE LLANO 058,Reach-1         , 4
Up Type= 0
Dn Type= 3
Dn Slope=0.02
Boundary for River Rch & Prof#=LITTLE LLANO 058,Reach-1         , 5
Up Type= 0
Dn Type= 3
Dn Slope=0.02
Boundary for River Rch & Prof#=LITTLE LLANO 058,Reach-1         , 6
Up Type= 0
Dn Type= 3
Dn Slope=0.02
Boundary for River Rch & Prof#=LITTLE LLANO 058,Reach-1         , 7
Up Type= 0
Dn Type= 3
Dn Slope=0.02
DSS Import GetInterval= 0
DSS Import GetPeak= 0
DSS Import FillOption= 0

--- LITTLE LLANO 058.g01 (geometry) ---

Geom Title=Existing Conditions
Program Version=4.10

River Reach=LITTLE LLANO 058,Reach-1
Reach XY= 30
      2849154.75       10285493.      2849085.25       10285080.
        2848766.       10284632.      2848783.25       10284240.
      2848613.25       10283375.      2848651.25       10283150.
      2848543.75       10282941.      2848592.25       10282632.
       2848564.5       10282243.        2848995.       10281316.
      2848977.75       10280542.      2849099.25       10280257.
      2849085.25       10279886.      2848842.25       10279587.
       2848550.5       10279504.      2848269.25       10279212.
       2848071.5       10279091.        2846929.       10278795.
       2846682.5       10278615.       2846755.5       10278000.
        2846686.       10277861.       2846484.5       10277757.
      2846425.75       10277615.        2846436.       10277000.
      2846224.25       10276761.      2846217.25       10276455.
      2846088.75       10275851.       2846130.5       10275625.
       2846533.5       10275217.       2846648.5       10274630.

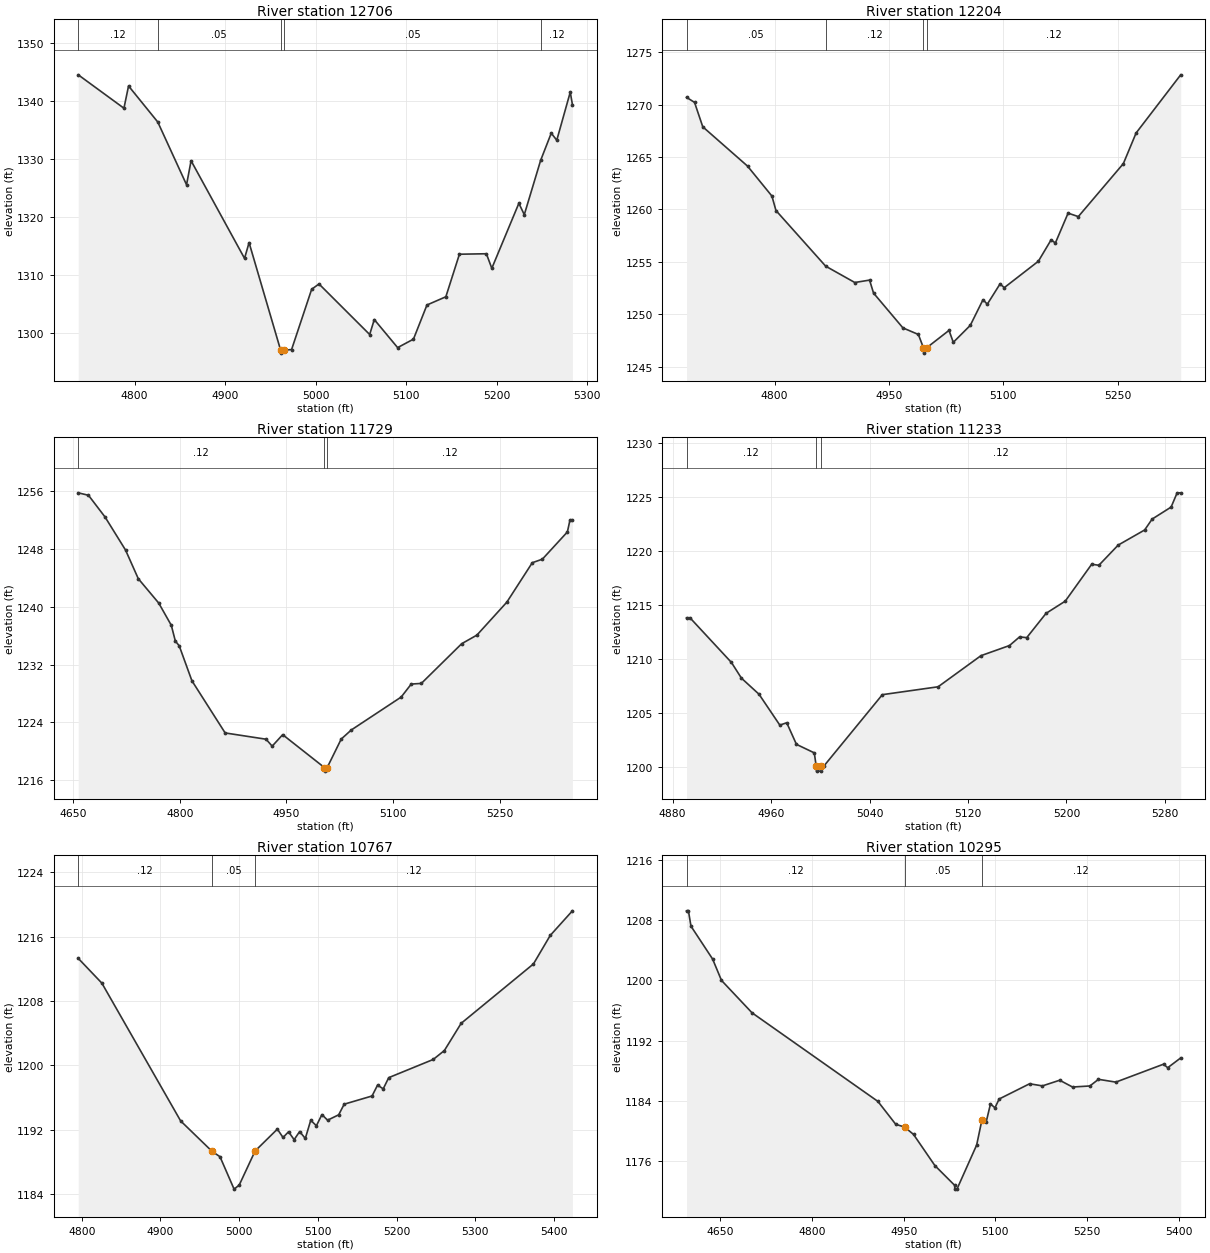
Type RM Length L Ch R = 1 ,12706   ,502,502,502
BEGIN DESCRIPTION:
LITTLE LLANO 058 25.0
END DESCRIPTION:
XS GIS Cut Line= 3
      2849278.88     10284930.37      2848928.79     10284982.78
      2848820.25     10285141.41
#Sta/Elev= 30
  4737.7 1344.56  4788.2  1338.8  4793.3 1342.64  4825.6 1336.42  4857.4  1325.6
  4862.4 1329.74  4921.5  1312.9  4926.5 1315.62  4961.4 1297.06  4961.6 1296.56
  4965.4 1297.06  4973.5 1297.18  4995.7 1307.58  5003.8 1308.49  5059.8 1299.77
  5064.9 1302.35  5090.7 1297.51  5108.2 1298.97  5123.1 1304.86    5144 1306.28
    5159 1313.62  5188.8  1313.7  5194.8 1311.19  5224.7  1322.4  5230.7 1320.44
  5248.8 1329.82  5260.5  1334.5  5266.6 1333.28  5281.5 1341.57  5283.9 1339.44
#Mann= 5 ,-1 , 0
  4737.7     .12       0  4825.6     .05       0  4961.4     .05       0
  4965.4     .05       0  5248.8     .12       0
Bank Sta=4961.4,4965.4
XS Rating Curve= 0 ,0
Exp/Cntr=0.3,0.1

Type RM Length L Ch R = 1 ,12204   ,475,475,475
BEGIN DESCRIPTION:
LITTLE LLANO 058 24.0
END DESCRIPTION:
XS GIS Cut Line= 3
      2849055.68     10284653.11       2848755.5       10284556.
      2848605.71     10284853.07
#Sta/Elev= 30
  4684.5 1270.69    4695 1270.21  4705.8 1267.88  4764.5 1264.13  4796.5 1261.27
  4801.8 1259.89    4867 1254.58  4905.2 1253.02  4924.6 1253.25  4929.8 1252.01
  4968.3 1248.69  4988.6 1248.06  4995.3 1246.78  4995.5 1246.28  4999.3 1246.78
  5028.8 1248.45  5034.4 1247.31  5056.7 1248.93  5073.4 1251.38    5079 1250.95
  5095.7 1252.88  5101.3 1252.53    5146 1255.05  5162.7 1257.09  5168.3 1256.79
    5185 1259.64  5198.4 1259.31  5257.5 1264.37  5274.2 1267.29  5332.7 1272.84
#Mann= 4 ,-1 , 0
  4684.5     .05       0    4867     .12       0  4995.3     .07       0
  4999.3     .12       0
Bank Sta=4995.3,4999.3
XS Rating Curve= 0 ,0
Exp/Cntr=0.3,0.1

Type RM Length L Ch R = 1 ,11729   ,496,496,496
BEGIN DESCRIPTION:
LITTLE LLANO 058 23.0
END DESCRIPTION:
XS GIS Cut Line= 3
      2849055.67     10283953.12       2848741.5       10284091.
      2848505.67     10284353.13
#Sta/Elev= 30
  4656.9 1255.81  4671.3 1255.47  4694.7 1252.45  4723.5 1247.88  4741.4 1243.92
  4770.2 1240.54  4787.9 1237.46  4793.6 1235.27    4799 1234.63  4816.9 1229.78
  4863.7 1222.55  4921.3 1221.68  4929.9 1220.72  4944.7 1222.31  5003.4 1217.76
  5003.6 1217.26  5007.4 1217.76  5027.1  1221.7  5041.3 1222.96  5111.5 1227.52
  5125.7 1229.32  5139.9 1229.41  5196.7 1234.91  5218.1  1236.1  5260.3 1240.67
  5296.1 1246.13  5310.3 1246.62  5345.5 1250.39  5349.2 1252.07  5352.6 1252.07
#Mann= 3 ,-1 , 0
  4656.9     .12       0  5003.4     .07       0  5007.4     .12       0
Bank Sta=5003.4,5007.4
XS Rating Curve= 0 ,0
Exp/Cntr=0.3,0.1

Type RM Length L Ch R = 1 ,11233   ,466,466,466
BEGIN DESCRIPTION:
LITTLE LLANO 058 22.0
END DESCRIPTION:
XS GIS Cut Line= 3
      2848755.72     10283653.13      2848658.25       10283605.
      2848405.68     10283753.12
#Sta/Elev= 30
  4891.3 1213.79  4894.1 1213.79  4927.8 1209.65  4935.9  1208.2  4950.2 1206.71
  4967.1 1203.85  4972.7 1204.07  4980.6 1202.07  4995.1 1201.28  4996.6 1200.09
  4996.9 1199.59  5000.4 1199.59  5000.6 1200.09  5003.1 1200.09  5050.4 1206.67
  5095.7  1207.4  5130.5 1210.28  5153.7 1211.22  5161.9 1212.02  5167.7 1211.95
  5183.4  1214.2    5199 1215.33  5220.5 1218.75  5226.3 1218.65    5242 1220.52
  5263.5 1221.92  5269.6 1222.93    5285 1224.04  5289.9 1225.36  5292.8 1225.36
#Mann= 3 ,-1 , 0
  4891.3     .12       0  4996.6     .07       0  5000.6     .12       0
Bank Sta=4996.6,5000.6
XS Rating Curve= 0 ,0
Exp/Cntr=0.3,0.1

Type RM Length L Ch R = 1 ,10767   ,472,472,472
BEGIN DESCRIPTION:
LITTLE LLANO 058 21.0
END DESCRIPTION:
XS GIS Cut Line= 3
      2848855.73     10283153.11      2848651.25       10283150.
      2848355.66     10283453.14
#Sta/Elev= 30
  4795.5  1213.3  4825.5 1210.22  4925.6 1193.09  4965.6  1189.3  4975.6 1188.64
  4993.5 1184.61    5000 1185.11  5020.2 1189.35  5048.5 1192.07  5055.7 1191.03
  5062.7 1191.74  5069.8 1190.76  5076.8 1191.77    5084 1190.91  5090.9 1193.17
  5098.1 1192.49  5105.1 1193.88  5112.3 1193.18  5126.4 1193.85  5133.4 1195.17
  5168.8 1196.19  5175.8 1197.54    5183 1197.08    5190 1198.47  5246.5 1200.73
  5260.7 1201.84    5282 1205.22  5373.9 1212.61  5395.2 1216.15  5423.4 1219.21
#Mann= 3 , 0 , 0
  4795.5     .12       0  4965.6     .05       0  5020.2     .12       0
Bank Sta=4965.6,5020.2
XS Rating Curve= 0 ,0
Exp/Cntr=0.3,0.1

Type RM Length L Ch R = 1 ,10295   ,469,469,469
BEGIN DESCRIPTION:
LITTLE LLANO 058 20.0
END DESCRIPTION:
XS GIS Cut Line= 3
      2848905.67      10282953.1      2848581.75       10282709.
      2848305.67     10283003.13
#Sta/Elev= 30
  4594.4 1209.22  4597.5 1209.22  4601.7 1207.18  4637.1 1202.82  4651.6 1199.99
  4701.6 1195.69  4907.7 1183.93  4936.9 1180.89  4951.4 1180.53    4966 1179.55
 5000.93 1175.42  5033.4 1172.79  5033.6 1172.29  5037.1 1172.29 5069.35 1178.14
  5077.8  1181.4  5085.1 1181.25    5092  1183.6  5099.3 1183.08  5106.2 1184.25
    5156 1186.27    5177 1185.99  5205.3 1186.74  5226.3 1185.84  5254.7 1185.98
  5268.8 1186.86  5297.2 1186.49  5375.3 1188.87  5382.1  1188.4  5403.4  1189.7
#Mann= 3 , 0 , 0
  4594.4     .12       0  4951.4     .05       0  5077.8     .12       0
Bank Sta=4951.4,5077.8
XS Rating Curve= 0 ,0
Exp/Cntr=0.3,0.1

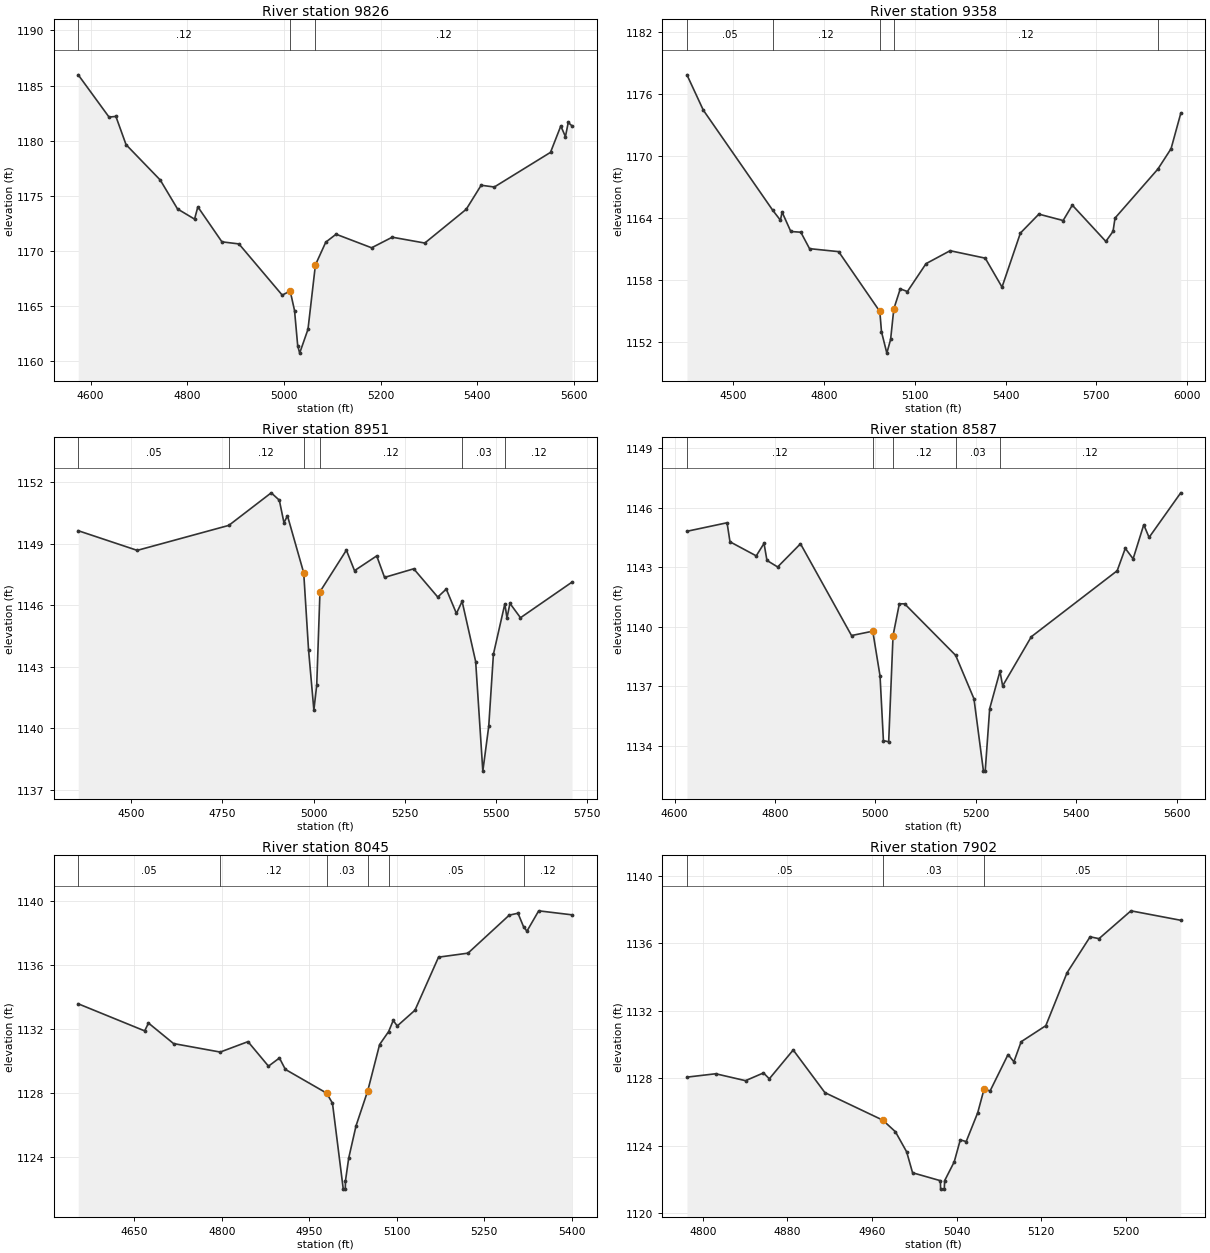
Type RM Length L Ch R = 1 ,9826    ,468,468,468
BEGIN DESCRIPTION:
LITTLE LLANO 058 19.0
END DESCRIPTION:
XS GIS Cut Line= 3
      2848855.69     10282553.12       2848564.5       10282243.
      2848055.66     10282553.13
#Sta/Elev= 30
  4574.6 1185.97  4638.3 1182.14  4652.5  1182.2  4673.5 1179.64  4744.3 1176.43
    4780 1173.81  4815.2 1172.89    4822    1174  4871.8 1170.83    4907 1170.64
  4996.5    1166    5013 1166.37    5022  1164.6  5028.5 1161.43  5032.6 1160.74
  5049.8  1162.9  5065.2 1168.74  5086.6  1170.8  5107.9 1171.52  5181.4 1170.29
  5224.1 1171.25  5291.4 1170.72  5377.1 1173.78    5408 1175.96  5435.2  1175.8
  5551.4 1178.94  5572.7 1181.33  5582.3 1180.37  5588.1 1181.65  5595.9 1181.34
#Mann= 3 , 0 , 0
  4574.6     .12       0    5013     .05       0  5065.2     .12       0
Bank Sta=5013,5065.2
XS Rating Curve= 0 ,0
Exp/Cntr=0.3,0.1

Type RM Length L Ch R = 1 ,9358    ,407,407,407
BEGIN DESCRIPTION:
LITTLE LLANO 058 18.0
END DESCRIPTION:
XS GIS Cut Line= 3
      2849005.69     10282403.12      2848724.25       10281813.
      2847805.69     10282153.11
#Sta/Elev= 30
  4346.2 1177.88  4400.2 1174.47  4629.6 1164.79  4655.4 1163.81  4660.9  1164.6
  4689.7 1162.72  4722.9 1162.65  4751.7 1161.06    4848 1160.77  4984.2 1154.98
  4989.7 1153.02  5007.4 1150.95  5019.9 1152.28  5030.5 1155.23  5051.8 1157.17
  5075.4 1156.91  5137.1 1159.61  5216.7 1160.86  5332.9 1160.14  5388.4 1157.34
  5449.2 1162.57  5510.3  1164.4  5590.5 1163.78  5620.9 1165.27  5731.8 1161.76
  5755.6 1162.73  5762.2 1164.02  5903.9 1168.76  5947.5 1170.73  5979.5 1174.14
#Mann= 5 ,-1 , 0
  4346.2     .05       0  4629.6     .12       0  4984.2     .05       0
  5030.5     .12       0  5903.9     .05       0
Bank Sta=4984.2,5030.5
XS Rating Curve= 0 ,0
Exp/Cntr=0.3,0.1

Type RM Length L Ch R = 1 ,8951    ,364,364,364
BEGIN DESCRIPTION:
LITTLE LLANO 058 17.0
END DESCRIPTION:
XS GIS Cut Line= 3
      2849497.67      10281769.8      2848772.83     10281400.86
      2848309.59     10281125.95
#Sta/Elev= 30
  4355.8 1149.64  4517.3 1148.68  4768.1  1149.9  4884.2 1151.49  4906.4 1151.13
  4919.1 1150.03  4928.7 1150.37  4973.2 1147.58  4986.4 1143.83    5001 1140.88
  5008.8  1142.1  5017.7 1146.66    5090 1148.69  5112.3 1147.69  5173.1 1148.41
  5194.5 1147.36  5274.4 1147.78  5340.2  1146.4  5363.5 1146.79  5391.3  1145.6
  5406.9 1146.19    5444 1143.25  5463.6  1137.9  5479.8 1140.09  5492.6 1143.61
  5523.9 1146.07  5529.7 1145.38  5537.9 1146.09  5566.7 1145.39  5707.8 1147.13
#Mann= 6 ,-1 , 0
  4355.8     .05       0  4768.1     .12       0  4973.2     .03       0
  5017.7     .12       0  5406.9     .03       0  5523.9     .12       0
Bank Sta=4973.2,5017.7
XS Rating Curve= 0 ,0
Exp/Cntr=0.3,0.1

Type RM Length L Ch R = 1 ,8587    ,542,542,542
BEGIN DESCRIPTION:
LITTLE LLANO 058 16.0
END DESCRIPTION:
XS GIS Cut Line= 3
      2849308.82      10281309.7      2849059.29     10281157.81
       2848406.1     10280932.12
#Sta/Elev= 30
  4624.7 1144.82  4704.6 1145.25  4710.4 1144.29  4762.7 1143.58  4778.2 1144.21
    4784 1143.35  4805.3 1143.02  4850.8 1144.19  4952.4 1139.56  4994.7 1139.78
  5009.2 1137.52  5015.9 1134.26  5026.4  1134.2  5035.1 1139.56  5047.6 1141.16
  5058.2 1141.16  5159.8 1138.56  5196.2 1136.37  5215.1 1132.72  5218.6 1132.72
  5227.5 1135.87    5248 1137.76  5253.3 1137.02  5310.4  1139.5  5481.4 1142.83
  5497.5 1143.96  5513.1 1143.43  5534.3 1145.15  5544.9 1144.51  5607.9 1146.76
#Mann= 5 ,-1 , 0
  4624.7     .12       0  4994.7     .03       0  5035.1     .12       0
  5159.8     .03       0    5248     .12       0
Bank Sta=4994.7,5035.1
XS Rating Curve= 0 ,0
Exp/Cntr=0.3,0.1

Type RM Length L Ch R = 1 ,8045    ,143,143,143
BEGIN DESCRIPTION:
LITTLE LLANO 058 15.0
END DESCRIPTION:
XS GIS Cut Line= 3
      2849305.68     10280853.11      2849102.69     10280608.76
      2848579.09      10280535.2
#Sta/Elev= 30
  4553.9 1133.58  4667.8 1131.89  4674.3 1132.38  4717.3  1131.1  4797.3 1130.57
  4844.9 1131.22    4880 1129.69  4898.8  1130.2  4908.9 1129.49  4979.6 1128.01
  4989.7 1127.38  5008.2 1122.02  5011.7 1122.02  5011.9 1122.52  5017.5 1123.95
  5030.1 1125.97  5050.3 1128.17  5070.5 1131.04    5086 1131.85  5093.8 1132.54
  5100.8  1132.2  5131.1 1133.18  5171.5 1136.49    5222 1136.74  5292.7 1139.11
  5307.7 1139.23  5317.2 1138.39    5323 1138.11  5343.2 1139.38  5400.3 1139.13
#Mann= 6 ,-1 , 0
  4553.9     .05       0  4797.3     .12       0  4979.6     .03       0
  5050.3     .12       0    5086     .05       0  5317.2     .12       0
Bank Sta=4979.6,5050.3
XS Rating Curve= 0 ,0
Exp/Cntr=0.3,0.1

Type RM Length L Ch R = 1 ,7902    ,251,251,251
BEGIN DESCRIPTION:
LITTLE LLANO 058 14.0
END DESCRIPTION:
XS GIS Cut Line= 3
      2849213.13     10280550.99      2848926.67      10280412.1
      2848778.78      10280427.1
#Sta/Elev= 30
  4784.9 1128.07  4812.1 1128.27  4840.3 1127.86  4857.3 1128.32  4862.8 1127.97
  4885.4 1129.68  4915.4 1127.15  4970.1 1125.52  4982.1 1124.83  4992.7 1123.64
  4998.3  1122.4  5024.6 1121.93  5024.8 1121.43  5028.3 1121.43  5028.6 1121.93
  5037.7 1123.05  5043.4 1124.35    5049 1124.25  5059.9 1125.96    5066 1127.38
  5071.6 1127.25  5088.6 1129.41  5094.1 1128.98    5101 1130.17  5124.3 1131.12
  5144.4 1134.26  5166.2 1136.39  5174.6 1136.28  5204.8 1137.93  5251.9 1137.37
#Mann= 3 , 0 , 0
  4784.9     .05       0  4970.1     .03       0    5066     .05       0
Bank Sta=4970.1,5066
XS Rating Curve= 0 ,0
Exp/Cntr=0.3,0.1

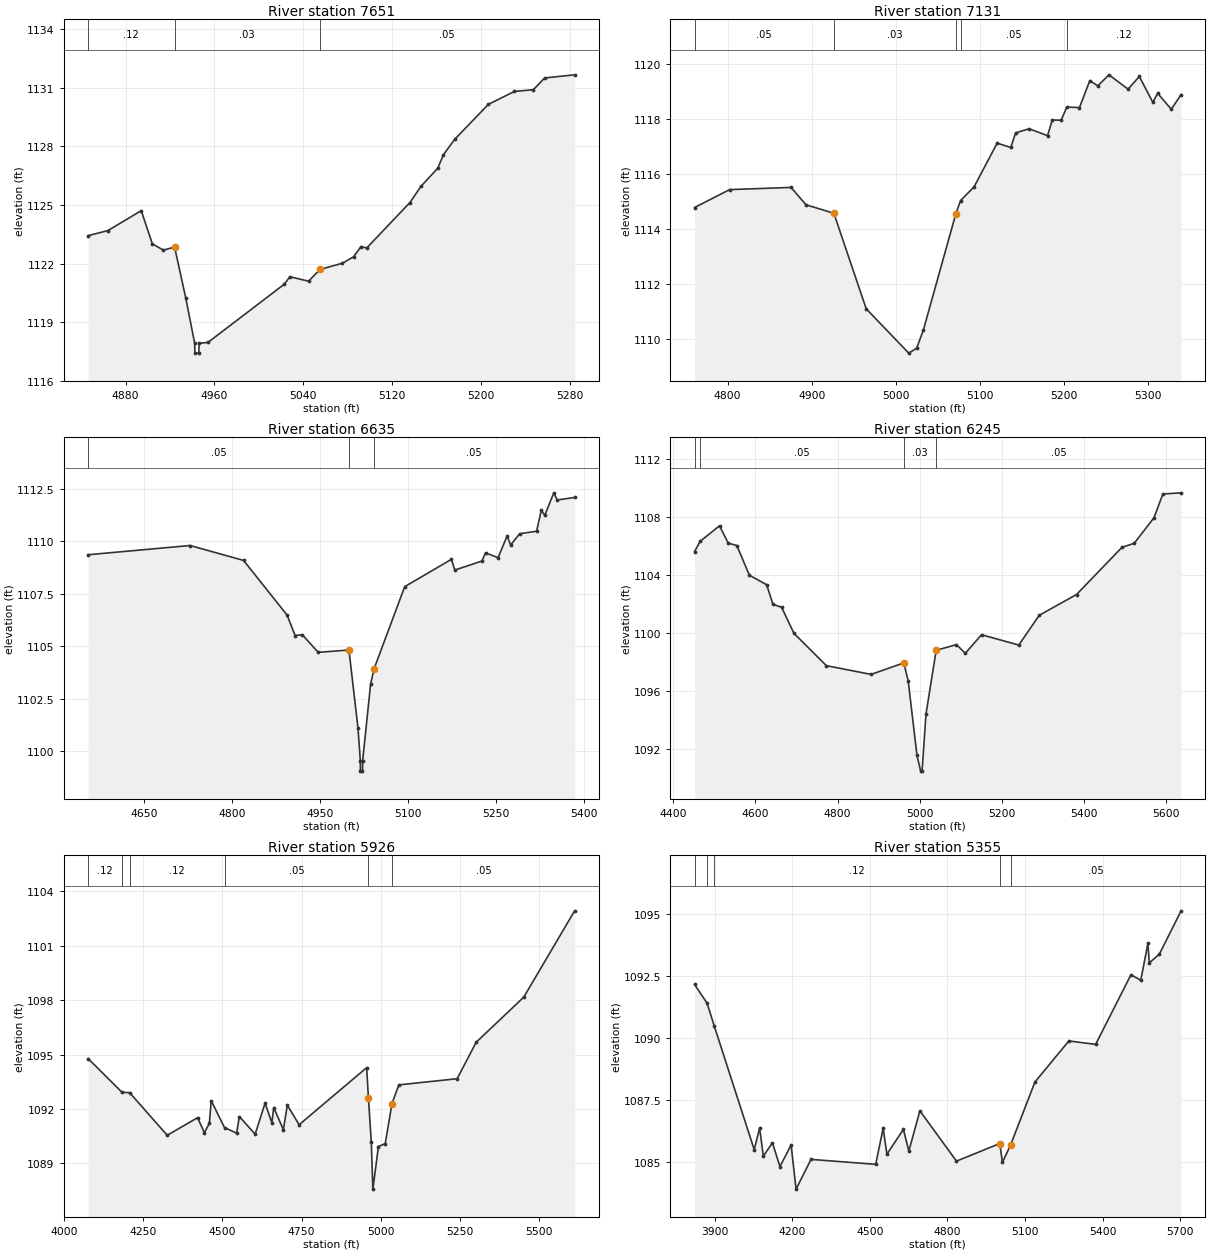
Type RM Length L Ch R = 1 ,7651    ,520,520,520
BEGIN DESCRIPTION:
Mapping XS 2df95d4b
END DESCRIPTION:
XS GIS Cut Line= 3
       2849243.5     10280227.64      2849095.94      10280223.3
      2848808.99     10280266.45
#Sta/Elev= 30
  4846.3 1123.43  4864.1 1123.69  4894.1 1124.71  4904.1 1123.01  4914.1 1122.69
  4924.1 1122.85  4934.1 1120.26  4942.2 1117.92  4942.4 1117.42  4945.9 1117.42
  4946.2 1117.92  4954.2 1117.97  5022.9 1120.95  5027.9 1121.33  5044.7  1121.1
  5054.9  1121.7  5075.1 1122.02  5085.2 1122.35  5091.9 1122.87    5097  1122.8
  5135.8 1125.12  5145.9 1125.96  5160.9 1126.88  5166.1 1127.58  5176.2 1128.36
  5206.5 1130.15  5229.9 1130.81    5247  1130.9  5257.1  1131.5  5284.1 1131.66
#Mann= 3 ,-1 , 0
  4846.3     .12       0  4924.1     .03       0  5054.9     .05       0
Bank Sta=4924.1,5054.9
XS Rating Curve= 0 ,0
Exp/Cntr=0.3,0.1

Type RM Length L Ch R = 1 ,7131    ,496,496,496
BEGIN DESCRIPTION:
LITTLE LLANO 058 13.0
END DESCRIPTION:
XS GIS Cut Line= 3
      2849187.06     10279713.32      2849025.55     10279734.81
      2848660.31     10279933.67
#Sta/Elev= 30
  4760.7 1114.78  4802.4 1115.43  4875.5 1115.51  4893.2 1114.88  4926.4 1114.57
 4964.89  1111.1  5015.5 1109.49 5024.94 1109.67  5032.9 1110.33  5071.4 1114.54
  5077.1 1115.03  5093.2 1115.53  5120.7 1117.12  5136.9 1116.96  5142.6 1117.49
  5158.7 1117.64  5180.6 1117.39  5186.3 1117.96  5196.7 1117.95  5203.6 1118.43
  5218.6 1118.41  5230.9 1119.39  5240.4  1119.2  5253.7  1119.6  5276.4 1119.08
  5289.8 1119.54  5305.9  1118.6  5311.6 1118.93  5327.8 1118.35  5339.5 1118.88
#Mann= 5 ,-1 , 0
  4760.7     .05       0  4926.4     .03       0  5071.4     .12       0
  5077.1     .05       0  5203.6     .12       0
Bank Sta=4926.4,5071.4
XS Rating Curve= 0 ,0
Exp/Cntr=0.3,0.1

Type RM Length L Ch R = 1 ,6635    ,390,390,390
BEGIN DESCRIPTION:
LITTLE LLANO 058 12.0
END DESCRIPTION:
XS GIS Cut Line= 3
      2848976.79      10279378.3      2848627.43     10279441.23
      2848382.51      10279848.7
#Sta/Elev= 30
  4554.1 1109.35    4728 1109.79  4819.4 1109.08  4893.6 1106.48  4907.4  1105.5
  4919.6 1105.54  4946.9  1104.7  4999.3 1104.81  5014.8 1101.08  5018.7 1099.54
  5018.9 1099.04  5022.4 1099.04  5022.7 1099.54  5036.2 1103.17    5042  1103.9
  5094.5 1107.83  5174.2 1109.13    5180 1108.62  5226.3 1109.05  5232.4 1109.44
  5253.8 1109.21  5269.4 1110.25  5275.2 1109.81  5290.7 1110.35  5319.6 1110.47
  5327.6 1111.47  5333.5 1111.23    5349  1112.3  5354.8 1111.96  5384.5 1112.08
#Mann= 3 , 0 , 0
  4554.1     .05       0  4999.3     .03       0    5042     .05       0
Bank Sta=4999.3,5042
XS Rating Curve= 0 ,0
Exp/Cntr=0.3,0.1

Type RM Length L Ch R = 1 ,6245    ,319,319,319
BEGIN DESCRIPTION:
LITTLE LLANO 058 11.0
END DESCRIPTION:
XS GIS Cut Line= 3
      2848728.72     10278923.26      2848330.12     10279180.81
      2848080.62     10279844.71
#Sta/Elev= 30
    4452  1105.6  4465.5  1106.3  4512.7 1107.37  4533.8 1106.18  4554.9 1106.01
  4585.3 1103.97  4627.5 1103.31  4642.7 1101.96  4663.8 1101.76  4693.7 1099.97
  4772.7 1097.74  4881.5 1097.14  4961.1 1097.93  4971.8 1096.69  4993.1 1091.57
  5002.1 1090.48  5005.6 1090.48    5015  1094.4  5039.9  1098.8  5089.3 1099.19
  5110.6 1098.59  5150.2 1099.87  5240.9 1099.16  5290.7 1101.21  5381.4 1102.64
  5491.7 1105.88  5521.9 1106.17    5570 1107.93  5591.4 1109.56  5635.8 1109.64
#Mann= 4 ,-1 , 0
    4452     .12       0  4465.5     .05       0  4961.1     .03       0
  5039.9     .05       0
Bank Sta=4961.1,5039.9
XS Rating Curve= 0 ,0
Exp/Cntr=0.3,0.1

Type RM Length L Ch R = 1 ,5926    ,571,571,571
BEGIN DESCRIPTION:
LITTLE LLANO 058 10.0
END DESCRIPTION:
XS GIS Cut Line= 3
      2848505.46     10278280.21      2847976.82     10279186.45
      2847942.97     10279673.42
#Sta/Elev= 30
  4075.5 1094.78  4182.6 1092.92  4206.7  1092.9  4325.4 1090.55  4421.4 1091.52
  4442.9 1090.69  4458.6 1091.21  4464.4 1092.46  4506.6 1090.97  4544.6 1090.67
  4553.5 1091.58  4603.3 1090.61  4634.6 1092.32  4656.2 1091.24    4662 1092.08
  4692.4 1090.86    4705 1092.21  4742.2 1091.13  4955.6 1094.28  4961.4 1092.58
  4970.3 1090.18  4975.3 1087.58  4992.8 1089.93  5014.3 1090.09  5035.8  1092.3
  5057.3 1093.33  5241.6 1093.67  5301.7 1095.68  5452.1 1098.17  5612.8 1102.93
#Mann= 6 ,-1 , 0
  4075.5     .12       0  4182.6     .05       0  4206.7     .12       0
  4506.6     .05       0  4961.4     .03       0  5035.8     .05       0
Bank Sta=4961.4,5035.8
XS Rating Curve= 0 ,0
Exp/Cntr=0.3,0.1

Type RM Length L Ch R = 1 ,5355    ,633,633,633
BEGIN DESCRIPTION:
LITTLE LLANO 058 9.0
END DESCRIPTION:
XS GIS Cut Line= 3
      2848328.42     10278152.57      2847539.32      10278777.6
       2847284.1     10279613.57
#Sta/Elev= 30
  3822.3 1092.17  3870.7 1091.41  3898.7 1090.48  4052.9  1085.5  4073.7 1086.38
  4088.1 1085.24  4123.3 1085.78  4152.2 1084.82  4195.5 1085.69  4214.6 1083.91
  4272.4 1085.11  4522.4 1084.91  4551.3 1086.37  4565.7 1085.32  4629.5 1086.32
  4650.6 1085.45  4693.3 1087.07  4834.7 1085.04    5002 1085.75  5012.5 1084.99
  5043.8 1085.69  5137.9 1088.23  5269.1 1089.89  5372.7 1089.75  5509.2 1092.56
  5547.2 1092.34  5574.8 1093.83    5580 1093.04  5618.9 1093.39    5703 1095.14
#Mann= 5 ,-1 , 0
  3822.3     .12       0  3870.7     .05       0  3898.7     .12       0
    5002     .05       0  5043.8     .05       0
Bank Sta=5002,5043.8
XS Rating Curve= 0 ,0
Exp/Cntr=0.3,0.1

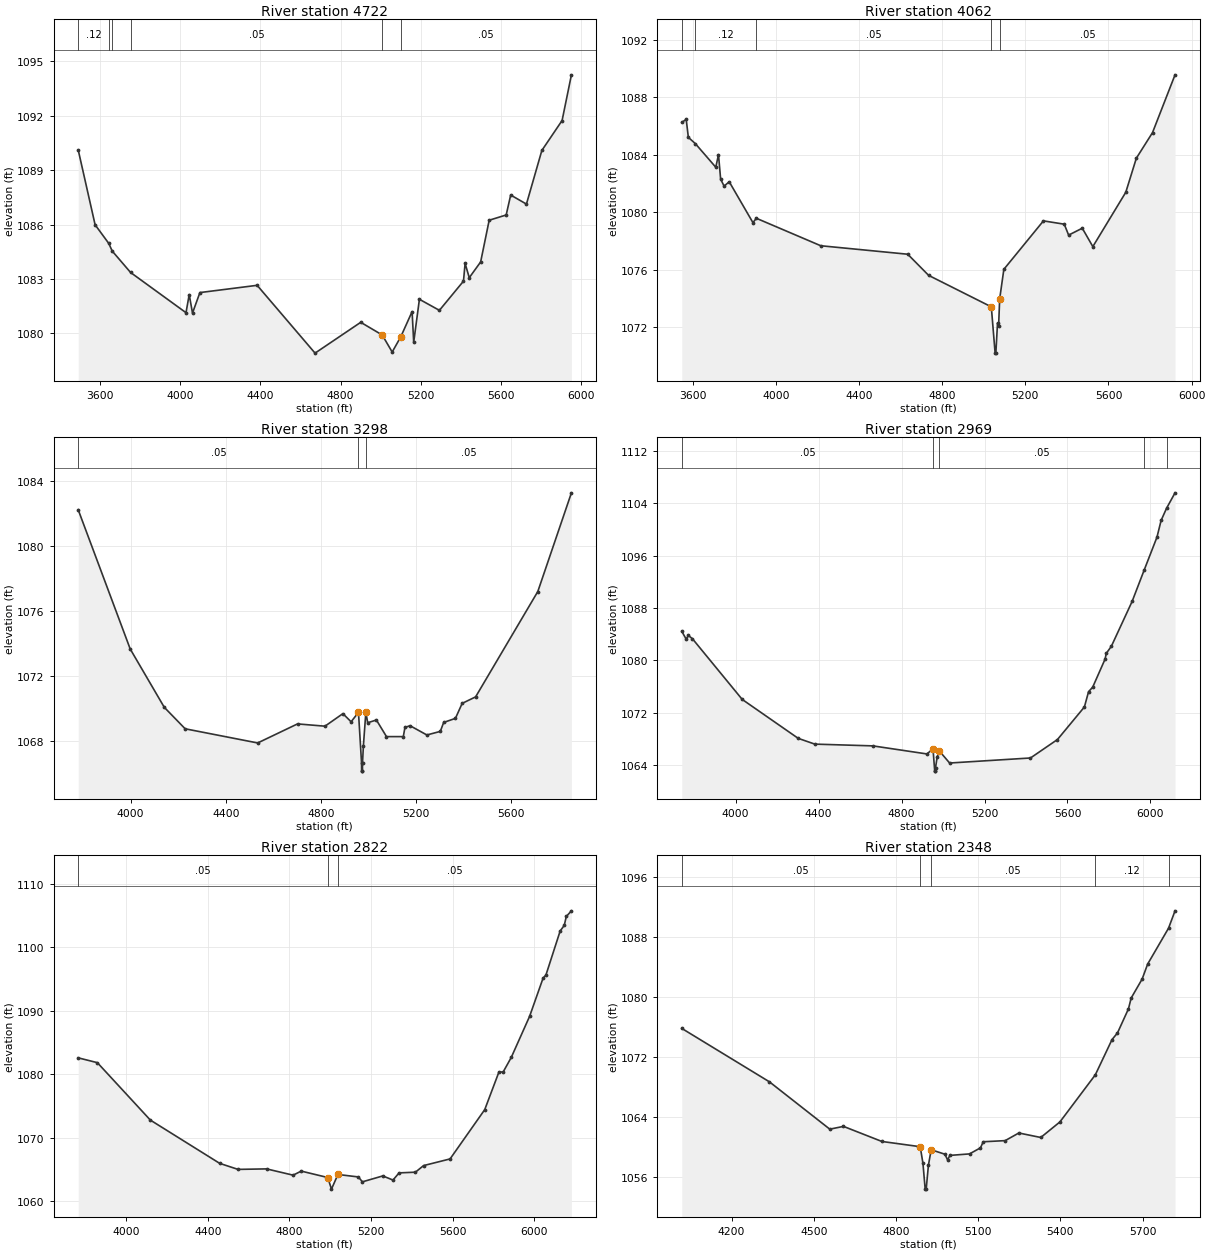
Type RM Length L Ch R = 1 ,4722    ,660,660,660
BEGIN DESCRIPTION:
LITTLE LLANO 058 8.0
END DESCRIPTION:
XS GIS Cut Line= 3
      2848213.82     10278108.32       2847023.7     10278595.31
      2846295.17     10279518.97
#Sta/Elev= 30
  3490.4 1090.12  3574.8 1085.99  3643.1 1084.96  3660.2 1084.54  3751.8 1083.36
  4028.6 1081.14  4044.6 1082.14    4061 1081.12    4098 1082.25  4383.7 1082.65
  4672.8 1078.91  4900.9 1080.61  5008.2 1079.91  5057.9 1078.97  5101.2 1079.82
  5157.3  1081.2  5165.3 1079.51  5193.8 1081.88  5293.6 1081.27  5413.8 1082.88
  5421.9 1083.86  5442.7 1083.07  5499.5 1083.94  5542.1 1086.24    5627 1086.53
  5649.5 1087.63  5728.1 1087.13  5805.1 1090.09  5906.1 1091.74  5952.7 1094.26
#Mann= 6 ,-1 , 0
  3490.4     .12       0  3643.1     .05       0  3660.2     .12       0
  3751.8     .05       0  5008.2     .03       0  5101.2     .05       0
Bank Sta=5008.2,5101.2
XS Rating Curve= 0 ,0
Exp/Cntr=0.3,0.1

Type RM Length L Ch R = 1 ,4062    ,764,764,764
BEGIN DESCRIPTION:
Mapping XS fa479590
END DESCRIPTION:
XS GIS Cut Line= 4
      2848146.14     10277905.19      2847114.84     10278181.25
      2846560.15     10278238.54        2845943.     10278660.39
#Sta/Elev= 30
  3547.3 1086.24  3568.5 1086.45  3578.8  1085.2  3612.7 1084.76  3710.8 1083.12
  3723.8    1084  3734.1 1082.29  3750.8 1081.81  3775.5 1082.11  3889.4 1079.27
  3906.1 1079.57  4215.8 1077.66  4634.2 1077.07  4734.7  1075.6  5036.3 1073.41
  5054.6 1070.19  5058.1 1070.19  5066.2 1072.29  5071.3 1072.05  5076.5 1073.96
  5096.6 1076.02    5287 1079.39  5387.2 1079.16  5408.2  1078.4  5473.9 1078.88
  5524.7  1077.6  5683.2 1081.38    5734 1083.75  5811.8 1085.53  5920.1 1089.55
#Mann= 5 ,-1 , 0
  3547.3     .05       0  3612.7     .12       0  3906.1     .05       0
  5036.3     .03       0  5076.5     .05       0
Bank Sta=5036.3,5076.5
XS Rating Curve= 0 ,0
Exp/Cntr=0.3,0.1

Type RM Length L Ch R = 1 ,3298    ,329,329,329
BEGIN DESCRIPTION:
LITTLE LLANO 058 7.0
END DESCRIPTION:
XS GIS Cut Line= 3
      2847605.72      10277303.1      2846425.75       10277615.
      2845805.69     10278203.11
#Sta/Elev= 30
  3779.5 1082.23  3998.3 1073.68  4141.6  1070.1  4229.5 1068.78  4534.6 1067.91
  4702.2 1069.08  4817.8 1068.94  4893.1 1069.71  4927.7 1069.21  4958.7 1069.79
  4971.6 1066.68  4971.9 1066.18  4975.4 1066.18  4975.6 1066.68  4979.4 1067.74
  4989.7  1069.8  4997.4 1069.15  5034.1 1069.32  5076.5  1068.3  5147.3  1068.3
  5154.2 1068.86  5175.6 1068.97  5246.4  1068.4    5303 1068.62  5317.1 1069.17
  5366.6 1069.42  5394.9 1070.34  5451.5 1070.74  5713.2 1077.21  5854.6 1083.27
#Mann= 3 , 0 , 0
  3779.5     .05       0  4958.7     .03       0  4989.7     .05       0
Bank Sta=4958.7,4989.7
XS Rating Curve= 0 ,0
Exp/Cntr=0.3,0.1

Type RM Length L Ch R = 1 ,2969    ,147,147,147
BEGIN DESCRIPTION:
LITTLE LLANO 058 6.0
END DESCRIPTION:
XS GIS Cut Line= 3
      2847677.03     10277281.22      2846619.76     10277286.43
      2845298.74     10277302.03
#Sta/Elev= 30
  3740.2 1084.42  3761.5 1083.22  3771.5  1083.8  3791.5 1083.29  4031.6 1074.01
  4301.6 1068.06  4381.6 1067.18  4661.6 1066.91  4921.6 1065.68  4951.6 1066.42
  4959.8 1063.05  4963.3 1063.05  4963.6 1063.55  4971.6 1065.22  4981.6 1066.15
  5031.6 1064.29  5421.6 1065.06  5551.6 1067.88  5681.6 1072.86  5701.6 1075.19
  5721.6 1075.89  5781.6  1080.2  5786.8 1081.04  5811.6 1082.14  5911.6 1088.99
  5969.2 1093.74  6031.6 1098.83  6051.6 1101.39  6077.8 1103.24  6118.6  1105.6
#Mann= 5 ,-1 , 0
  3740.2     .05       0  4951.6     .03       0  4981.6     .05       0
  5969.2     .12       0  6077.8     .05       0
Bank Sta=4951.6,4981.6
XS Rating Curve= 0 ,0
Exp/Cntr=0.3,0.1

Type RM Length L Ch R = 1 ,2822    ,474,474,474
BEGIN DESCRIPTION:
Mapping XS 538025e8
END DESCRIPTION:
XS GIS Cut Line= 2
      2847679.61     10277177.05      2845260.51     10277114.56
#Sta/Elev= 30
  3763.5 1082.56  3857.5  1081.8  4117.5 1072.75  4457.7 1065.93  4547.7 1064.98
  4687.7 1065.06  4817.8 1064.07  4857.8 1064.71  4987.8  1063.7  5006.1 1061.87
  5037.8 1064.18  5137.9 1063.79  5157.9 1063.02  5257.9 1063.95  5307.9  1063.3
  5337.9 1064.43    5418 1064.54    5458 1065.58    5588 1066.63  5758.1  1074.4
  5828.1 1080.36  5848.1 1080.31  5888.1 1082.62  5978.2  1089.1  6044.4 1095.13
  6058.2  1095.6  6128.2 1102.56  6148.2 1103.43  6158.2 1104.84  6183.4 1105.73
#Mann= 3 , 0 , 0
  3763.5     .05       0  4987.8     .03       0  5037.8     .05       0
Bank Sta=4987.8,5037.8
XS Rating Curve= 0 ,0
Exp/Cntr=0.3,0.1

Type RM Length L Ch R = 1 ,2348    ,499,499,499
BEGIN DESCRIPTION:
LITTLE LLANO 058 5.0
END DESCRIPTION:
XS GIS Cut Line= 3
      2847205.72     10276753.11      2846224.25       10276761.
      2845405.69     10276753.11
#Sta/Elev= 30
  4018.5  1075.8  4338.5 1068.67  4558.6 1062.36  4608.6 1062.73  4748.6 1060.72
  4888.6 1060.02  4898.6  1057.8  4906.7 1054.36  4910.4 1054.36  4918.6 1057.56
  4928.6 1059.61  4978.6 1059.02  4988.6 1058.26  4996.8 1058.86  5068.6 1059.06
  5108.6 1059.87  5118.6 1060.68  5198.6 1060.83  5248.6 1061.85  5328.6 1061.25
  5398.6 1063.33  5527.7 1069.61  5588.6 1074.31  5608.6  1075.2  5648.6 1078.41
  5658.6 1079.86  5698.6 1082.39  5718.6 1084.38    5795 1089.18  5818.6 1091.49
#Mann= 5 ,-1 , 0
  4018.5     .05       0  4888.6     .05       0  4928.6     .05       0
  5527.7     .12       0    5795     .05       0
Bank Sta=4888.6,4928.6
XS Rating Curve= 0 ,0
Exp/Cntr=0.3,0.1

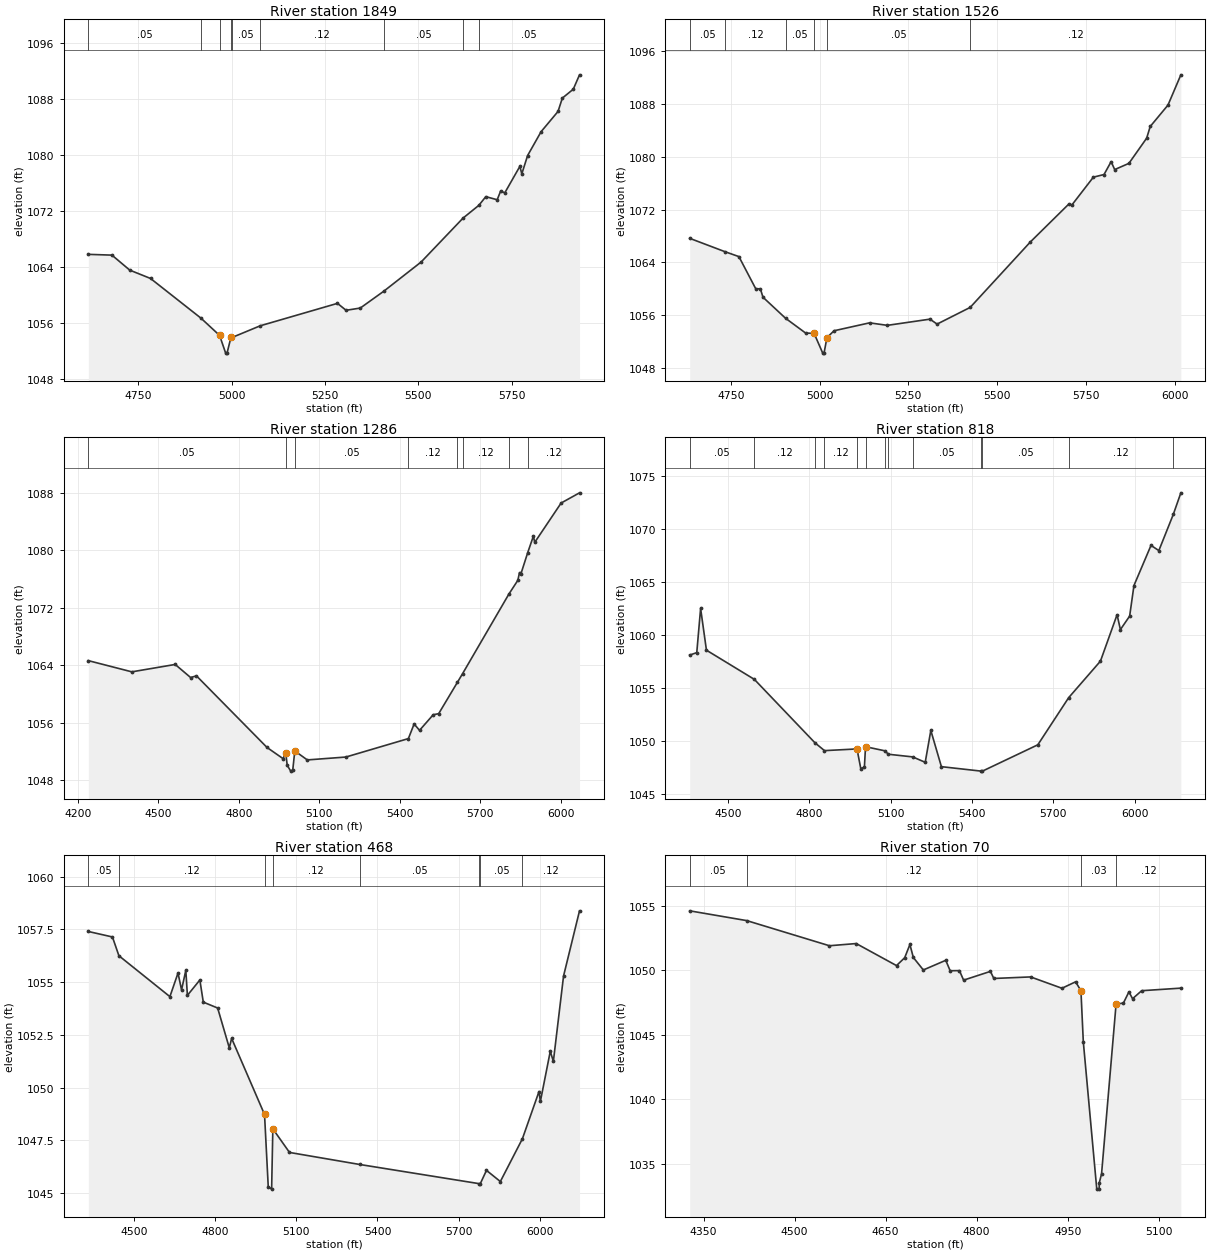
Type RM Length L Ch R = 1 ,1849    ,323,323,323
BEGIN DESCRIPTION:
LITTLE LLANO 058 4.0
END DESCRIPTION:
XS GIS Cut Line= 3
      2846546.81     10276179.67      2846278.61     10276249.97
      2845259.25      10276447.6
#Sta/Elev= 30
  4616.5  1065.8  4679.7 1065.69  4727.4 1063.55  4783.1 1062.36  4918.1  1056.7
    4968 1054.24  4984.3 1051.71    4988 1051.71  4998.6 1053.99  5000.4 1053.92
  5076.9 1055.61  5283.8 1058.81  5306.8 1057.82  5344.9 1058.14  5407.8 1060.54
  5507.9 1064.71  5620.1 1070.97  5662.4 1072.79  5681.1 1074.03  5711.6 1073.59
  5720.7 1074.81    5732 1074.58  5772.4 1078.36  5777.5 1077.28  5793.1  1079.9
  5829.2  1083.3  5874.6 1086.19  5886.1 1088.09  5915.4 1089.36  5932.1 1091.41
#Mann= 9 ,-1 , 0
  4616.5     .05       0  4918.1     .12       0    4968     .03       0
  4998.6     .12       0  5000.4     .05       0  5076.9     .12       0
  5407.8     .05       0  5620.1     .12       0  5662.4     .05       0
Bank Sta=4968,4998.6
XS Rating Curve= 0 ,0
Exp/Cntr=0.3,0.1

Type RM Length L Ch R = 1 ,1526    ,240,240,240
BEGIN DESCRIPTION:
LITTLE LLANO 058 3.0
END DESCRIPTION:
XS GIS Cut Line= 3
       2846455.7     10276003.12      2846265.59     10275953.09
      2845079.42     10275992.11
#Sta/Elev= 30
  4634.3 1067.65  4734.4 1065.61  4772.9 1064.88  4820.4    1060  4833.3    1060
  4840.8 1058.72  4904.4 1055.53  4960.9 1053.29  4984.7 1053.25    5009 1050.25
  5012.7 1050.25  5020.9  1052.6  5040.9 1053.64    5141 1054.84    5191 1054.46
  5311.1  1055.4  5331.1 1054.65  5424.3 1057.18    5594 1067.11  5701.3  1072.8
  5711.3 1072.74  5771.3 1076.92  5801.3 1077.32  5821.3 1079.27  5831.3 1078.07
  5871.4 1079.01  5921.4 1082.83  5931.4  1084.6  5981.4 1087.84  6017.7 1092.43
#Mann= 6 ,-1 , 0
  4634.3     .05       0  4734.4     .12       0  4904.4     .05       0
  4984.7     .03       0  5020.9     .05       0  5424.3     .12       0
Bank Sta=4984.7,5020.9
XS Rating Curve= 0 ,0
Exp/Cntr=0.3,0.1

Type RM Length L Ch R = 1 ,1286    ,468,468,468
BEGIN DESCRIPTION:
LITTLE LLANO 058 2.0
END DESCRIPTION:
XS GIS Cut Line= 3
      2846781.23     10276026.02      2846276.01     10275755.18
      2845039.82     10275515.75
#Sta/Elev= 30
  4238.5 1064.64  4400.7 1063.08  4562.5 1064.11    4620 1062.29  4641.9 1062.52
  4905.2 1052.55  4964.9    1051    4975 1051.77 4980.42 1050.07  4993.5 1049.26
 5001.12 1049.42  5008.7 1052.07  5055.3 1050.82  5199.1 1051.22  5432.5 1053.79
  5453.8 1055.82  5474.1 1054.94  5525.1 1057.11  5545.5 1057.26  5615.5 1061.63
  5634.7 1062.83  5807.3  1073.9  5840.8 1075.82    5847  1076.9  5852.1  1076.7
  5877.7 1079.68  5898.8 1081.97  5903.9 1081.11  6002.3 1086.58  6070.9    1088
#Mann= 8 ,-1 , 0
  4238.5     .05       0    4975     .03       0  5008.7     .05       0
  5432.5     .12       0  5615.5     .05       0  5634.7     .12       0
  5807.3     .05       0  5877.7     .12       0
Bank Sta=4975,5008.7
XS Rating Curve= 0 ,0
Exp/Cntr=0.3,0.1

Type RM Length L Ch R = 1 ,818     ,350,350,350
BEGIN DESCRIPTION:
Mapping XS d5794dca
END DESCRIPTION:
XS GIS Cut Line= 4
      2846856.07     10275799.77      2846495.72     10275406.67
      2845971.62     10275242.89      2845269.03     10275438.95
#Sta/Elev= 30
    4359  1058.1  4385.1 1058.33  4399.3 1062.49  4420.8 1058.56  4597.6 1055.81
    4821 1049.84  4856.2  1049.1  4976.1 1049.26  4990.1 1047.41 5003.52 1047.55
  5007.6 1049.47  5079.5 1049.08  5091.7 1048.76  5181.6 1048.51  5227.8    1048
  5248.5    1051  5287.5 1047.59  5434.4 1047.17  5438.8 1047.17  5643.2 1049.65
    5757 1054.09  5874.2 1057.53  5935.5  1061.9  5947.8  1060.5  5981.9 1061.77
  5997.8 1064.65  6060.7 1068.43  6089.6 1067.94  6142.8 1071.34  6170.8 1073.38
#Mann= 13 ,-1 , 0
    4359     .05       0  4597.6     .12       0    4821     .05       0
  4856.2     .12       0  4976.1     .03       0  5007.6     .12       0
  5079.5     .05       0  5091.7     .12       0  5181.6     .05       0
  5434.4     .07       0  5438.8     .05       0    5757     .12       0
  6142.8     .05       0
Bank Sta=4976.1,5007.6
XS Rating Curve= 0 ,0
Exp/Cntr=0.3,0.1

Type RM Length L Ch R = 1 ,468     ,398,398,398
BEGIN DESCRIPTION:
Mapping XS 14a8095e
END DESCRIPTION:
XS GIS Cut Line= 3
       2846960.9     10275570.28      2846697.88     10275114.55
      2845440.34     10274825.55
#Sta/Elev= 30
  4330.7  1057.4  4419.8 1057.14  4443.7 1056.25  4632.3 1054.31  4662.3 1055.43
  4675.4 1054.63  4691.2 1055.56    4697 1054.37  4743.1  1055.1  4755.8 1054.05
  4808.9 1053.77    4852 1051.88  4860.6 1052.33  4982.3 1048.72    4996  1045.3
 5008.52 1045.18    5013 1048.04  5074.6 1046.92  5333.9 1046.35  5775.8 1045.44
  5780.3 1045.44  5803.1 1046.07  5854.4 1045.54    5936 1047.57  5997.4 1049.81
  6002.5 1049.34  6039.1 1051.72  6050.5 1051.24  6088.2 1055.29  6147.2 1058.38
#Mann= 8 ,-1 , 0
  4330.7     .05       0  4443.7     .12       0  4982.3     .03       0
    5013     .12       0  5333.9     .05       0  5775.8     .05       0
  5780.3     .05       0    5936     .12       0
Bank Sta=4982.3,5013
XS Rating Curve= 0 ,0
Exp/Cntr=0.3,0.1

Type RM Length L Ch R = 1 ,70      ,0,0,0
BEGIN DESCRIPTION:
LITTLE LLANO 058 1.0
END DESCRIPTION:
XS GIS Cut Line= 3
      2846959.34     10275287.66      2846659.94     10274711.18
      2846526.93     10274622.23
#Sta/Elev= 30
    4327 1054.62  4421.1 1053.86  4557.3 1051.91  4601.5 1052.08  4667.9 1050.37
  4681.4 1050.98    4690 1052.01  4695.6    1051  4712.1 1050.03  4749.1 1050.78
  4756.3 1049.97  4771.6 1049.98  4778.5 1049.24  4822.7 1049.92  4828.3 1049.37
    4889 1049.49  4940.6 1048.61  4963.1 1049.11  4971.9 1048.42  4975.8 1044.46
    4998 1033.02  5001.9 1033.02  5002.2 1033.52  5005.9 1034.21  5029.8 1047.36
    5042 1047.47    5051 1048.33    5057  1047.8    5072 1048.42  5136.6 1048.62
#Mann= 4 ,-1 , 0
    4327     .05       0  4421.1     .12       0  4971.9     .03       0
  5029.8     .12       0
Bank Sta=4971.9,5029.8
XS Rating Curve= 0 ,0
Exp/Cntr=0.3,0.1

Chan Stop Cuts=-1
Use User Specified Reach Order=0
Composite Channel Slope=5