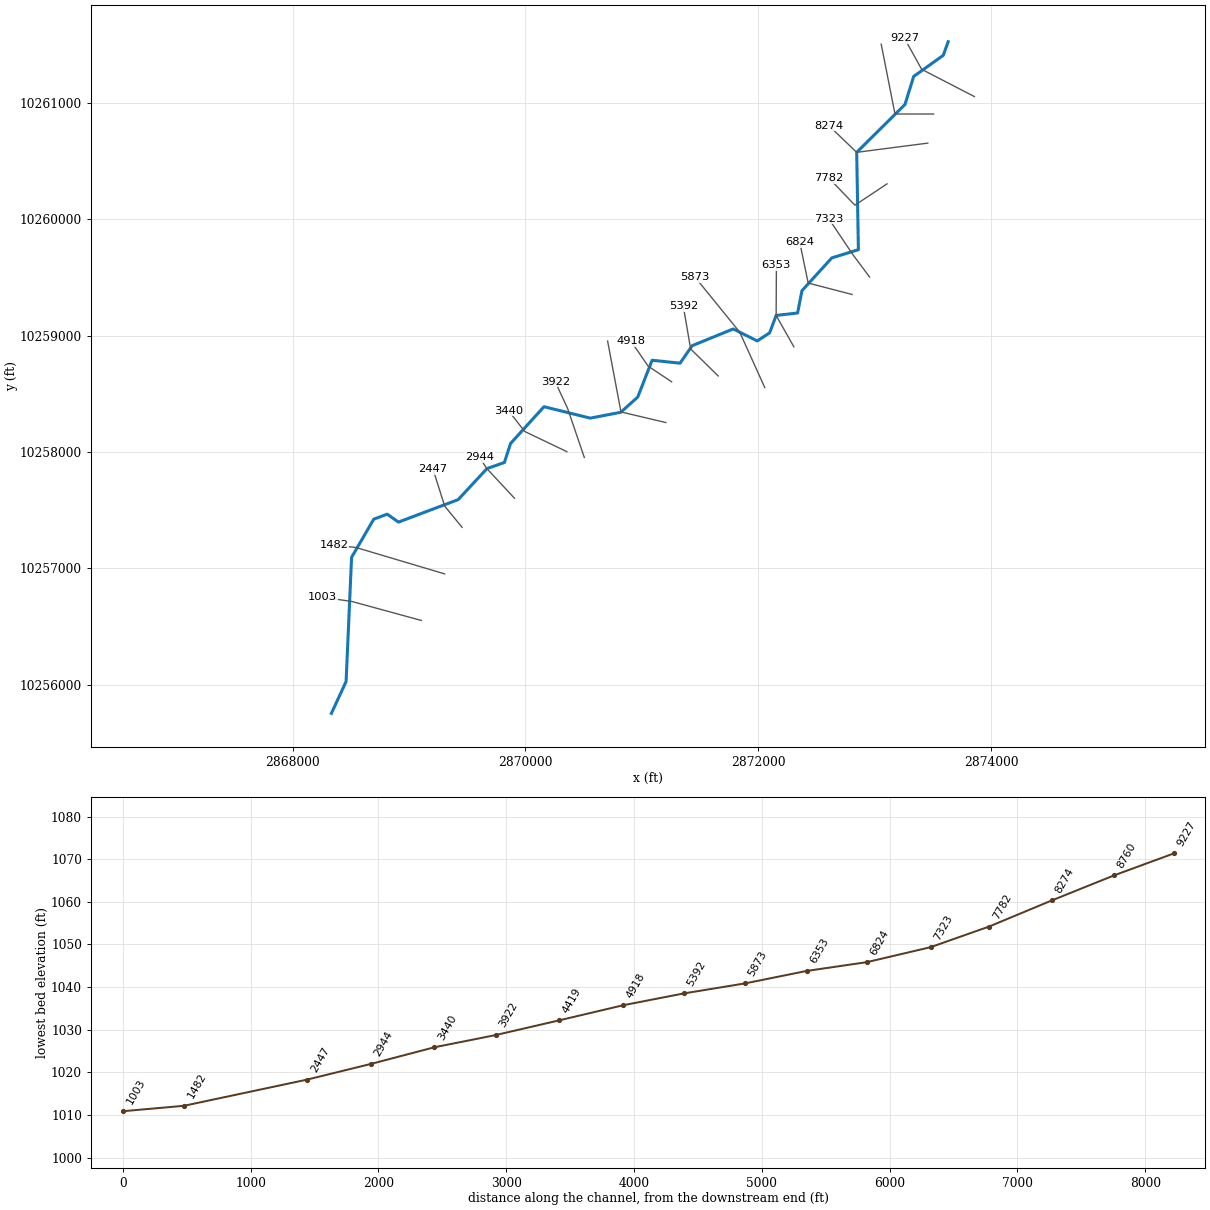
--- LITTLE LLANO 062.prj (project) ---

Proj Title=LITTLE LLANO 062 Base Level Engineering
Current Plan=p01
Default Exp/Contr=0.3,0.1
English Units
Geom File=g01
Flow File=f01
Plan File=p01
BEGIN DESCRIPTION:
LITTLE LLANO 062
END DESCRIPTION:

--- LITTLE LLANO 062.p01 (plan) ---

Plan Title=Multiple Run
Short Identifier=Multiple
Geom File=g01
Flow File=f01
Subcritical Flow
K Sum by GR= 0
Std Step Tol= 0.01
Critical Tol= 0.01
Num of Std Step Trials= 20
Max Error Tol= 0.3
Flow Tol Ratio= 0.001
Split Flow NTrial= 30
Split Flow Tol= 0.02
Split Flow Ratio= 0.02
Log Output Level= 0
Friction Slope Method= 1
Unsteady Friction Slope Method= 2
Unsteady Bridges Friction Slope Method= 1
Parabolic Critical Depth
Global Vel Dist=  1 , 1 , 1
Global Log Level= 0
CheckData=True
Encroach Param= -1, 0, 0, 0
BEGIN DESCRIPTION:
Multiple Run
END DESCRIPTION:

--- LITTLE LLANO 062.f01 (steady flow) ---

Flow Title=Multiple
Number of Profiles=7
Profile Names=10-year,25-year,50-year,1pct_min,100-year,1pct_plu,500-year
River Rch & RM= LITTLE LLANO 062,Reach-1,9227
     421     672     676     517     861    1435    1121
River Rch & RM= LITTLE LLANO 062,Reach-1,1482
     485     784     863     567     989    1726    1290
Boundary for River Rch & Prof#=LITTLE LLANO 062,Reach-1,1
Up Type=0
Dn Type=3
Dn Slope=0.005
Boundary for River Rch & Prof#=LITTLE LLANO 062,Reach-1,2
Up Type=0
Dn Type=3
Dn Slope=0.005
Boundary for River Rch & Prof#=LITTLE LLANO 062,Reach-1,3
Up Type=0
Dn Type=3
Dn Slope=0.005
Boundary for River Rch & Prof#=LITTLE LLANO 062,Reach-1,4
Up Type=0
Dn Type=3
Dn Slope=0.005
Boundary for River Rch & Prof#=LITTLE LLANO 062,Reach-1,5
Up Type=0
Dn Type=3
Dn Slope=0.005
Boundary for River Rch & Prof#=LITTLE LLANO 062,Reach-1,6
Up Type=0
Dn Type=3
Dn Slope=0.005
Boundary for River Rch & Prof#=LITTLE LLANO 062,Reach-1,7
Up Type=0
Dn Type=3
Dn Slope=0.005

--- LITTLE LLANO 062.g01 (geometry) ---

Geom Title=Existing Conditions

River Reach=LITTLE LLANO 062,Reach-1
Reach XY= 30
      2873630.75     10261524.00      2873588.75     10261407.00
      2873334.50     10261226.00      2873260.00     10260985.00
      2872845.25     10260574.00      2872859.75     10259738.00
      2872631.25     10259667.00      2872375.25     10259386.00
      2872337.50     10259194.00      2872153.25     10259173.00
      2872097.25     10259023.00      2871991.00     10258954.00
      2871784.75     10259057.00      2871431.50     10258913.00
      2871328.25     10258763.00      2871087.75     10258788.00
      2870964.75     10258472.00      2870818.50     10258341.00
      2870556.50     10258291.00      2870159.25     10258389.00
      2869872.00     10258073.00      2869819.00     10257910.00
      2869669.00     10257857.00      2869422.00     10257591.00
      2868909.50     10257398.00      2868812.75     10257466.00
      2868697.00     10257423.00      2868506.50     10257095.00
      2868459.50     10256029.00      2868333.25     10255755.00

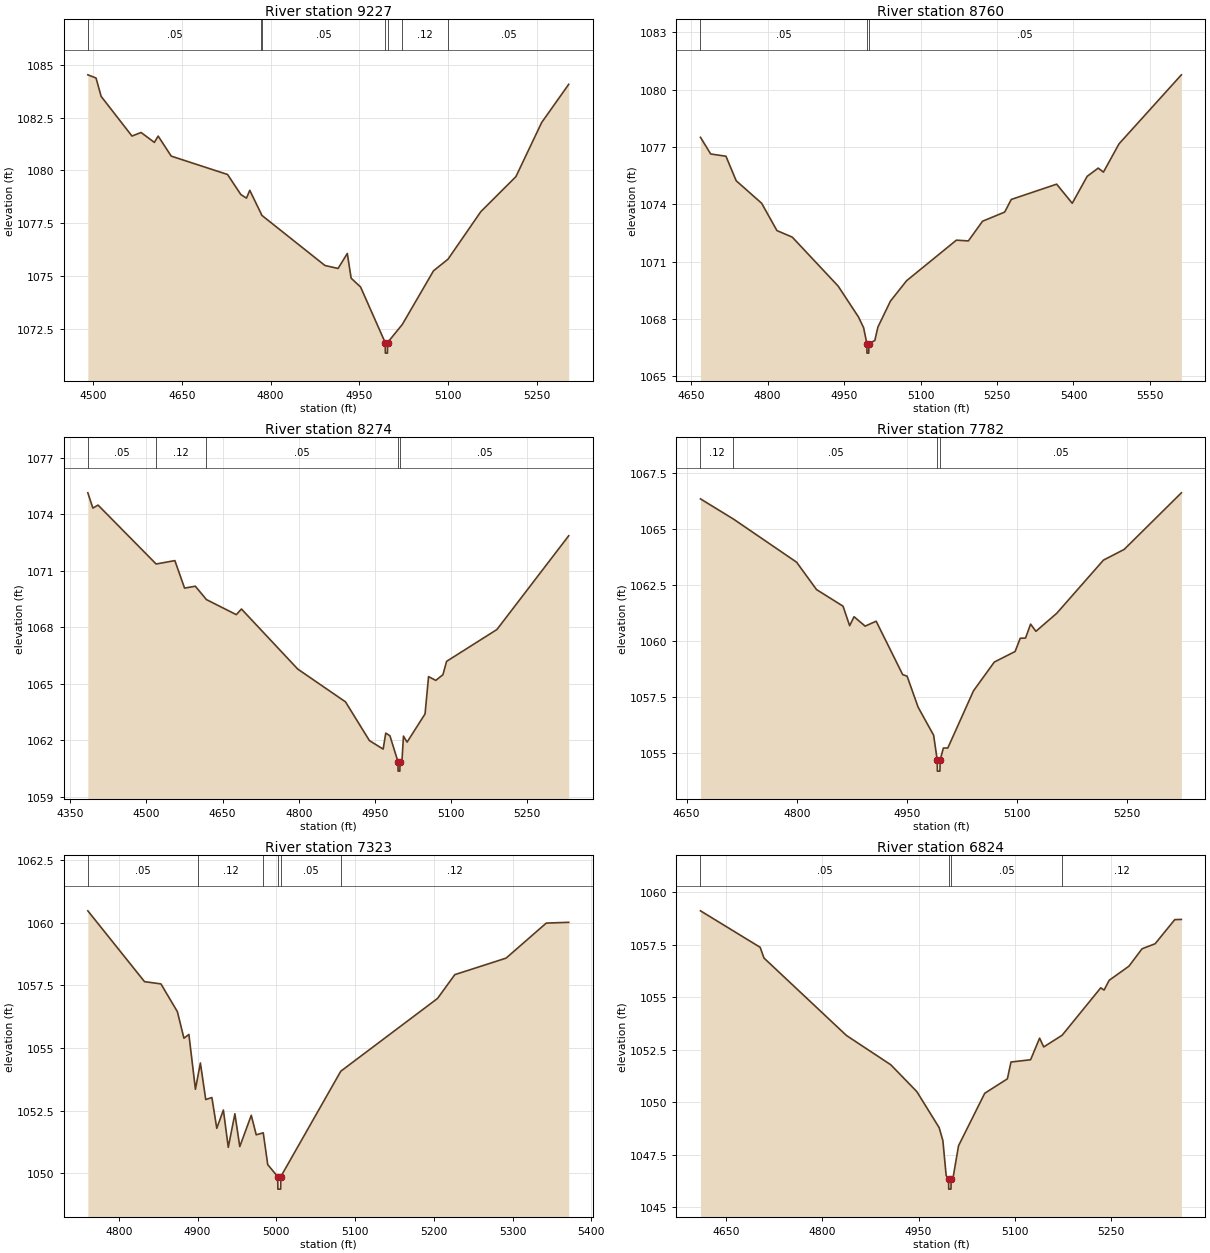
Type RM Length L Ch R = 1,9227,467,467,467
BEGIN DESCRIPTION:
LITTLE LLANO 062 17.0
END DESCRIPTION:
XS GIS Cut Line= 3
      2873855.67     10261053.12      2873403.25     10261287.00
      2873255.68     10261553.12
#Sta/Elev= 30
  4490.7 1084.53  4504.6 1084.38  4513.2 1083.51  4565.4 1081.63  4580.7 1081.80
  4603.3 1081.33  4609.7 1081.63  4631.8 1080.68  4727.1 1079.81  4749.6 1078.86
  4759.1 1078.69  4764.7 1079.06  4784.3 1077.93  4784.9 1077.88  4891.9 1075.50
  4914.1 1075.36  4929.7 1076.07  4936.2 1074.90  4952.2 1074.48  4993.8 1071.85
  4994.1 1071.35  4997.6 1071.35  4997.8 1071.85  5022.8 1072.71  5075.6 1075.25
  5100.1 1075.80  5155.6 1078.05  5215.0 1079.71  5258.5 1082.27  5304.3 1084.08
#Mann=7,-1,0
  4490.7    0.05       0  4784.3    0.12       0  4784.9    0.05       0
  4993.8    0.05       0  4997.8    0.05       0  5022.8    0.12       0
  5100.1    0.05       0
Bank Sta=4993.8,4997.8
Exp/Cntr=0.3,0.1

Type RM Length L Ch R = 1,8760,486,486,486
BEGIN DESCRIPTION:
LITTLE LLANO 062 16.0
END DESCRIPTION:
XS GIS Cut Line= 3
      2873505.70     10260903.11      2873174.00     10260903.00
      2873055.68     10261503.15
#Sta/Elev= 30
  4668.3 1077.50  4688.3 1076.63  4718.3 1076.51  4738.3 1075.23  4788.3 1074.05
  4818.3 1072.62  4848.3 1072.28  4938.3 1069.72  4978.3 1068.10  4988.3 1067.54
  4994.7 1066.71  4994.9 1066.21  4998.4 1066.21  4998.7 1066.71  5010.3 1066.87
  5016.3 1067.57  5040.9 1068.93  5072.7 1070.00  5170.3 1072.12  5193.8 1072.08
  5221.6 1073.11  5265.1 1073.59  5278.0 1074.25  5367.0 1075.05  5397.6 1074.05
  5426.9 1075.46  5448.6 1075.89  5458.8 1075.68  5489.4 1077.16  5611.7 1080.77
#Mann=3,-1,0
  4668.3    0.05       0  4994.7    0.05       0  4998.7    0.05       0
Bank Sta=4994.7,4998.7
Exp/Cntr=0.3,0.1

Type RM Length L Ch R = 1,8274,492,492,492
BEGIN DESCRIPTION:
LITTLE LLANO 062 15.0
END DESCRIPTION:
XS GIS Cut Line= 3
      2873455.65     10260653.11      2872845.25     10260574.00
      2872605.68     10260803.12
#Sta/Elev= 30
  4384.5 1075.13  4394.5 1074.32  4404.6 1074.48  4519.0 1071.35  4555.9 1071.53
  4575.0 1070.07  4596.2 1070.17  4618.1 1069.46  4676.9 1068.66  4687.0 1068.96
  4797.9 1065.77  4891.9 1064.03  4939.1 1061.97  4966.1 1061.52  4971.2 1062.37
  4979.4 1062.23  4995.3 1060.85  4995.5 1060.35  4999.0 1060.35  4999.3 1060.85
  5003.0 1060.85  5006.1 1062.21  5013.2 1061.89  5048.6 1063.39  5055.5 1065.37
  5069.7 1065.17  5083.8 1065.47  5091.0 1066.18  5190.1 1067.87  5331.5 1072.85
#Mann=5,-1,0
  4384.5    0.05       0  4519.0    0.12       0  4618.1    0.05       0
  4995.3    0.05       0  4999.3    0.05       0
Bank Sta=4995.3,4999.3
Exp/Cntr=0.3,0.1

Type RM Length L Ch R = 1,7782,459,459,459
BEGIN DESCRIPTION:
LITTLE LLANO 062 14.0
END DESCRIPTION:
XS GIS Cut Line= 3
      2873105.72     10260303.14      2872830.00     10260120.00
      2872605.69     10260353.10
#Sta/Elev= 30
  4669.0 1066.34  4713.9 1065.44  4799.8 1063.52  4826.9 1062.30  4863.0 1061.56
  4872.0 1060.69  4878.0 1061.09  4893.1 1060.67  4908.1 1060.89  4944.2 1058.51
  4950.2 1058.44  4965.2 1057.06  4986.3 1055.81  4991.2 1054.71  4991.4 1054.21
  4994.9 1054.21  4995.2 1054.71  4999.6 1055.24  5005.6 1055.24  5040.6 1057.79
  5068.9 1059.07  5097.2 1059.54  5104.2 1060.13  5111.4 1060.14  5118.3 1060.76
  5125.5 1060.44  5153.8 1061.24  5217.4 1063.61  5245.7 1064.09  5323.5 1066.61
#Mann=4,-1,0
  4669.0    0.12       0  4713.9    0.05       0  4991.2    0.05       0
  4995.2    0.05       0
Bank Sta=4991.2,4995.2
Exp/Cntr=0.3,0.1

Type RM Length L Ch R = 1,7323,499,499,499
BEGIN DESCRIPTION:
LITTLE LLANO 062 13.0
END DESCRIPTION:
XS GIS Cut Line= 3
      2872955.70     10259503.09      2872812.75     10259695.00
      2872605.70     10260003.09
#Sta/Elev= 30
  4760.7 1060.48  4832.7 1057.65  4853.5 1057.56  4874.4 1056.45  4882.7 1055.39
  4889.0 1055.54  4897.3 1053.35  4900.4 1053.87  4903.6 1054.40  4910.4 1052.94
  4918.2 1053.02  4924.4 1051.79  4932.8 1052.52  4939.0 1051.03  4947.4 1052.37
  4953.6 1051.06  4968.2 1052.31  4974.5 1051.53  4983.4 1051.61  4989.1 1050.34
  5001.7 1049.86  5002.0 1049.36  5005.5 1049.36  5005.7 1049.86  5081.8 1054.07
  5204.7 1056.98  5226.6 1057.93  5291.7 1058.59  5342.7 1059.99  5371.2 1060.02
#Mann=6,-1,0
  4760.7    0.05       0  4900.4    0.12       0  4983.4    0.05       0
  5001.7    0.05       0  5005.7    0.05       0  5081.8    0.12       0
Bank Sta=5001.7,5005.7
Exp/Cntr=0.3,0.1

Type RM Length L Ch R = 1,6824,471,471,471
BEGIN DESCRIPTION:
LITTLE LLANO 062 12.0
END DESCRIPTION:
XS GIS Cut Line= 3
      2872805.70     10259353.11      2872428.50     10259451.00
      2872355.68     10259803.15
#Sta/Elev= 30
  4610.3 1059.12  4703.3 1057.38  4709.2 1056.87  4837.6 1053.18  4906.8 1051.78
  4947.4 1050.50  4982.2 1048.78  4988.0 1048.16  4993.1 1046.50  4996.9 1046.35
  4997.1 1045.85  5000.6 1045.85  5000.9 1046.35  5003.6 1046.35  5012.4 1047.92
  5053.2 1050.42  5088.5 1051.11  5094.1 1051.91  5124.7 1052.02  5138.7 1053.05
  5145.1 1052.63  5173.9 1053.19  5234.0 1055.45  5239.1 1055.34  5247.2 1055.81
  5277.9 1056.48  5298.3 1057.31  5318.7 1057.55  5349.3 1058.70  5359.6 1058.71
#Mann=4,-1,0
  4610.3    0.05       0  4996.9    0.03       0  5000.9    0.05       0
  5173.9    0.12       0
Bank Sta=4996.9,5000.9
Exp/Cntr=0.3,0.1

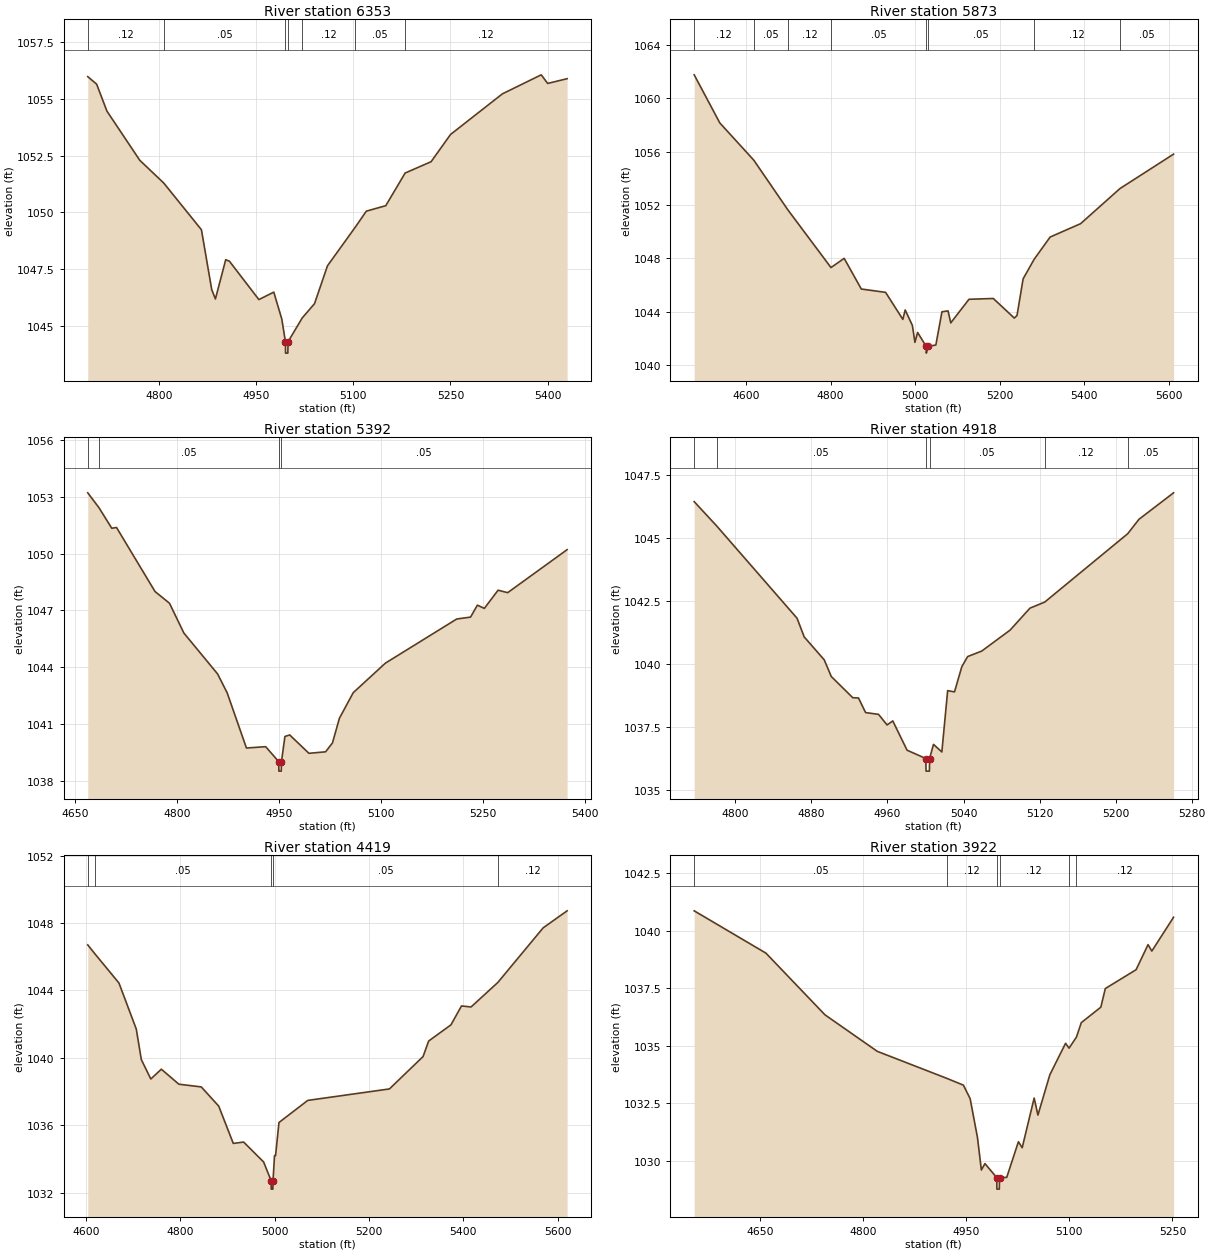
Type RM Length L Ch R = 1,6353,480,480,480
BEGIN DESCRIPTION:
LITTLE LLANO 062 11.0
END DESCRIPTION:
XS GIS Cut Line= 3
      2872305.70     10258903.08      2872153.25     10259173.00
      2872155.68     10259603.09
#Sta/Elev= 30
  4690.0 1055.98  4703.7 1055.65  4719.6 1054.46  4770.4 1052.29  4807.3 1051.29
  4865.5 1049.23  4881.4 1046.59  4887.1 1046.18  4903.0 1047.91  4908.8 1047.84
  4954.2 1046.15  4977.2 1046.48  4989.6 1045.29  4995.2 1044.29  4995.4 1043.79
  4998.9 1043.79  4999.2 1044.29  5021.1 1045.34  5040.1 1045.97  5060.1 1047.64
  5103.2 1049.35  5120.1 1050.05  5150.1 1050.29  5180.0 1051.73  5220.1 1052.23
  5250.1 1053.43  5330.1 1055.22  5390.1 1056.06  5400.1 1055.68  5430.1 1055.89
#Mann=7,-1,0
  4690.0    0.12       0  4807.3    0.05       0  4995.2    0.05       0
  4999.2    0.05       0  5021.1    0.12       0  5103.2    0.05       0
  5180.0    0.12       0
Bank Sta=4995.2,4999.2
Exp/Cntr=0.3,0.1

Type RM Length L Ch R = 1,5873,481,481,481
BEGIN DESCRIPTION:
LITTLE LLANO 062 10.0
END DESCRIPTION:
XS GIS Cut Line= 3
      2872055.69     10258553.09      2871840.75     10259029.00
      2871455.67     10259503.12
#Sta/Elev= 30
  4477.8 1061.76  4538.4 1058.15  4618.6 1055.36  4699.2 1051.63  4801.1 1047.30
  4832.3 1047.99  4872.8 1045.69  4930.2 1045.44  4971.0 1043.41  4976.5 1044.12
  4993.5 1042.96  4999.5 1041.69  5005.9 1042.43  5026.2 1041.38  5026.5 1040.88
  5030.2 1041.38  5049.0 1041.49  5063.4 1043.98  5077.8 1044.05  5084.2 1043.15
  5127.3 1044.92  5184.8 1044.98  5234.4 1043.51  5240.8 1043.70  5255.2 1046.45
  5281.1 1047.91  5319.1 1049.59  5391.0 1050.59  5484.3 1053.23  5610.8 1055.81
#Mann=8,-1,0
  4477.8    0.12       0  4618.6    0.05       0  4699.2    0.12       0
  4801.1    0.05       0  5026.2    0.05       0  5030.2    0.05       0
  5281.1    0.12       0  5484.3    0.05       0
Bank Sta=5026.2,5030.2
Exp/Cntr=0.3,0.1

Type RM Length L Ch R = 1,5392,474,474,474
BEGIN DESCRIPTION:
LITTLE LLANO 062 9.0
END DESCRIPTION:
XS GIS Cut Line= 3
      2871655.65     10258653.15      2871419.00     10258885.00
      2871355.69     10259253.09
#Sta/Elev= 30
  4668.7 1053.21  4685.3 1052.42  4704.0 1051.34  4711.0 1051.38  4767.6 1048.00
  4788.9 1047.38  4810.0 1045.81  4859.6 1043.65  4873.7 1042.65  4902.0 1039.74
  4930.3 1039.81  4949.5 1039.02  4949.7 1038.52  4953.2 1038.52  4953.5 1039.02
  4958.6 1040.35  4965.6 1040.43  4993.9 1039.46  5018.4 1039.54  5028.5 1040.01
  5038.7 1041.31  5059.0 1042.66  5106.3 1044.22  5211.2 1046.55  5231.5 1046.65
  5241.6 1047.28  5251.8 1047.11  5272.0 1048.07  5286.1 1047.94  5373.5 1050.21
#Mann=4,-1,0
  4668.7    0.12       0  4685.3    0.05       0  4949.5    0.05       0
  4953.5    0.05       0
Bank Sta=4949.5,4953.5
Exp/Cntr=0.3,0.1

Type RM Length L Ch R = 1,4918,499,499,499
BEGIN DESCRIPTION:
LITTLE LLANO 062 8.0
END DESCRIPTION:
XS GIS Cut Line= 3
      2871255.72     10258603.09      2871053.25     10258738.00
      2870905.66     10258953.14
#Sta/Elev= 30
  4756.7 1046.43  4780.3 1045.47  4864.9 1041.81  4872.4 1041.07  4893.5 1040.16
  4900.9 1039.50  4923.5 1038.66  4929.5 1038.65  4937.0 1038.07  4950.6 1038.00
  4959.6 1037.58  4965.6 1037.74  4980.6 1036.58  5000.3 1036.25  5000.6 1035.75
  5004.1 1035.75  5004.3 1036.25  5008.4 1036.81  5017.2 1036.51  5023.3 1038.94
  5030.5 1038.89  5038.2 1039.89  5044.3 1040.29  5059.2 1040.51  5089.0 1041.34
  5109.9 1042.21  5125.4 1042.45  5212.7 1045.16  5224.5 1045.73  5260.9 1046.78
#Mann=6,-1,0
  4756.7    0.12       0  4780.3    0.05       0  5000.3    0.03       0
  5004.3    0.05       0  5125.4    0.12       0  5212.7    0.05       0
Bank Sta=5000.3,5004.3
Exp/Cntr=0.3,0.1

Type RM Length L Ch R = 1,4419,497,497,497
BEGIN DESCRIPTION:
LITTLE LLANO 062 7.0
END DESCRIPTION:
XS GIS Cut Line= 3
      2871205.72     10258253.10      2870820.50     10258344.00
      2870705.69     10258953.07
#Sta/Elev= 30
  4604.2 1046.70  4619.1 1046.18  4670.3 1044.44  4707.0 1041.71  4717.7 1039.90
  4737.8 1038.75  4760.1 1039.33  4797.3 1038.44  4844.7 1038.28  4881.7 1037.14
  4912.5 1034.93  4934.5 1035.01  4976.8 1033.83  4992.7 1032.72  4992.9 1032.22
  4996.4 1032.22  4996.7 1032.72  4999.9 1034.21  5002.1 1034.21  5009.3 1036.17
  5070.3 1037.48  5243.3 1038.16  5314.6 1040.08  5326.4 1041.00  5373.7 1041.96
  5396.0 1043.08  5416.3 1043.02  5472.9 1044.47  5569.0 1047.71  5619.8 1048.72
#Mann=5,-1,0
  4604.2    0.12       0  4619.1    0.05       0  4992.7    0.03       0
  4996.7    0.05       0  5472.9    0.12       0
Bank Sta=4992.7,4996.7
Exp/Cntr=0.3,0.1

Type RM Length L Ch R = 1,3922,482,482,482
BEGIN DESCRIPTION:
LITTLE LLANO 062 6.0
END DESCRIPTION:
XS GIS Cut Line= 3
      2870505.70     10257953.08      2870361.75     10258375.00
      2870255.67     10258603.14
#Sta/Elev= 30
  4554.2 1040.87  4658.6 1039.03  4744.4 1036.35  4820.6 1034.76  4921.4 1033.59
  4945.9 1033.29  4955.7 1032.70  4966.3 1031.02  4972.0 1029.60  4977.2 1029.88
  4994.4 1029.27  4994.6 1028.77  4998.1 1028.77  4998.4 1029.27  5008.9 1029.28
  5025.9 1030.83  5031.4 1030.57  5048.8 1032.73  5054.3 1031.99  5071.6 1033.74
  5094.5 1035.11  5099.6 1034.90  5110.3 1035.38  5117.4 1036.01  5145.8 1036.68
  5152.3 1037.49  5197.1 1038.31  5214.5 1039.40  5220.0 1039.12  5251.6 1040.59
#Mann=6,-1,0
  4554.2    0.05       0  4921.4    0.12       0  4994.4    0.07       0
  4998.4    0.12       0  5099.6    0.05       0  5110.3    0.12       0
Bank Sta=4994.4,4998.4
Exp/Cntr=0.3,0.1

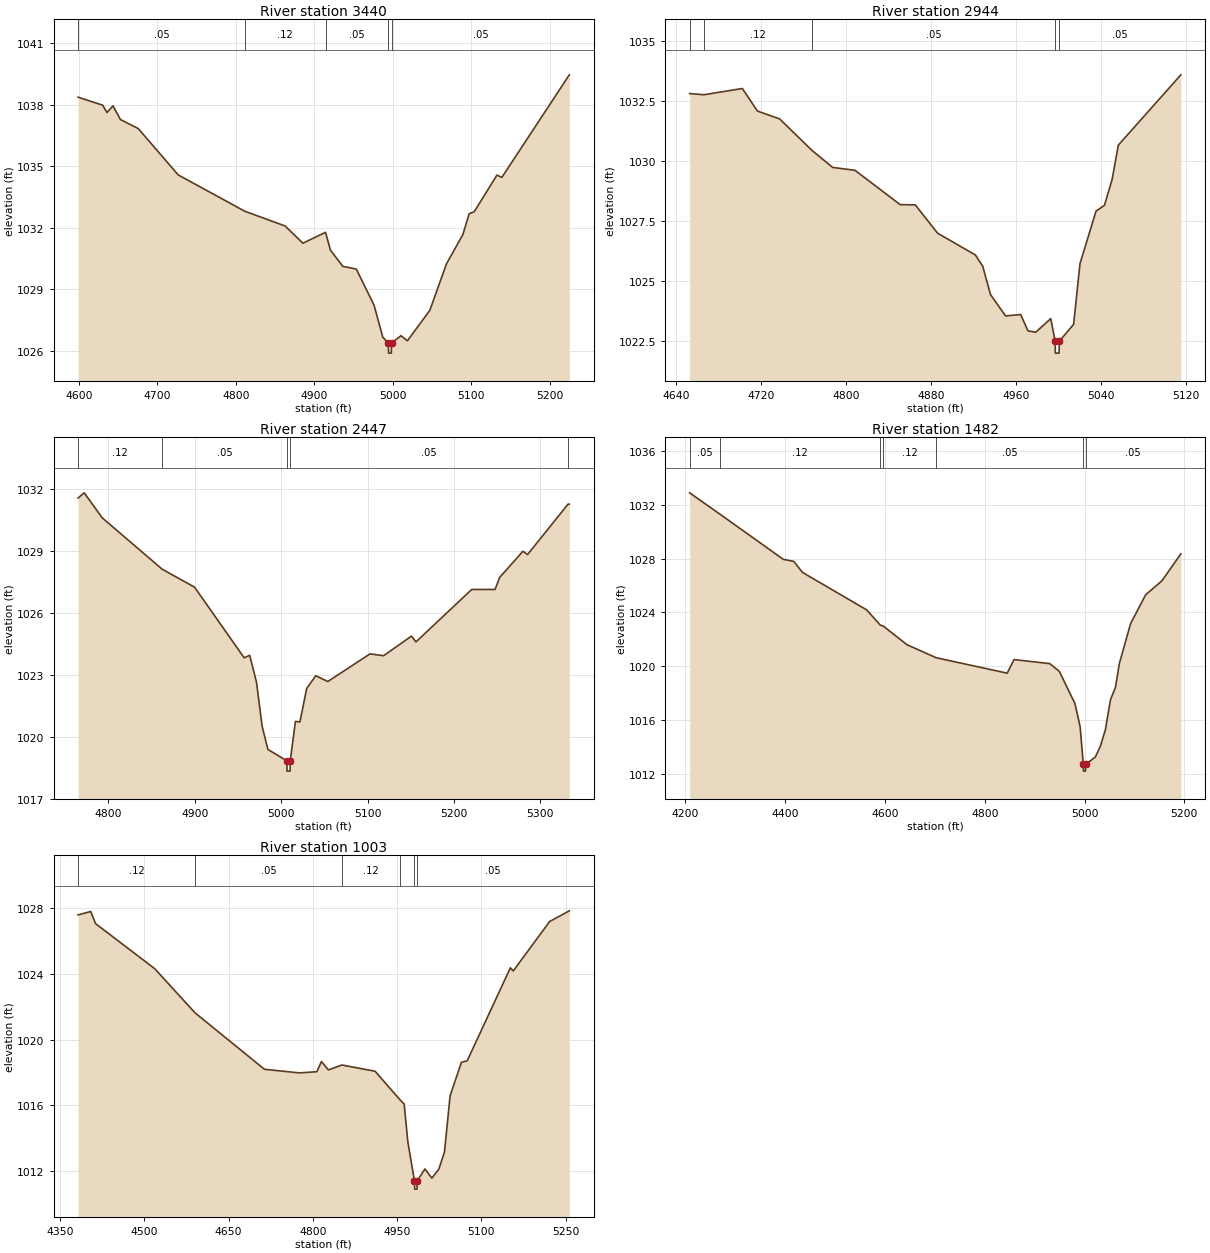
Type RM Length L Ch R = 1,3440,496,496,496
BEGIN DESCRIPTION:
LITTLE LLANO 062 5.0
END DESCRIPTION:
XS GIS Cut Line= 3
      2870355.70     10258003.10      2869994.00     10258176.00
      2869855.70     10258353.09
#Sta/Elev= 30
  4599.1 1038.37  4630.4 1037.98  4635.9 1037.62  4643.5 1037.95  4653.0 1037.28
  4675.7 1036.84  4726.6 1034.58  4811.3 1032.81  4862.7 1032.09  4885.4 1031.25
  4914.2 1031.78  4920.5 1030.91  4936.3 1030.12  4953.4 1029.99  4976.0 1028.23
  4987.2 1026.66  4994.3 1026.39  4994.5 1025.89  4998.0 1025.89  4998.3 1026.39
  5010.4 1026.74  5018.5 1026.49  5047.1 1027.98  5068.2 1030.24  5089.1 1031.67
  5097.2 1032.69  5103.5 1032.78  5132.5 1034.57  5138.8 1034.46  5224.7 1039.46
#Mann=5,-1,0
  4599.1    0.05       0  4811.3    0.12       0  4914.2    0.05       0
  4994.3    0.05       0  4998.3    0.05       0
Bank Sta=4994.3,4998.3
Exp/Cntr=0.3,0.1

Type RM Length L Ch R = 1,2944,497,497,497
BEGIN DESCRIPTION:
LITTLE LLANO 062 4.0
END DESCRIPTION:
XS GIS Cut Line= 3
      2869905.68     10257603.11      2869669.00     10257857.00
      2869605.68     10257953.12
#Sta/Elev= 30
  4652.9 1032.81  4666.4 1032.76  4702.5 1033.02  4716.7 1032.08  4737.7 1031.75
  4768.0 1030.44  4787.5 1029.73  4808.5 1029.61  4851.0 1028.18  4865.2 1028.17
  4886.2 1026.99  4921.8 1026.08  4928.7 1025.61  4936.0 1024.43  4950.2 1023.54
  4964.4 1023.60  4971.2 1022.92  4978.5 1022.86  4992.7 1023.43  4996.8 1022.49
  4997.0 1021.99  5000.5 1021.99  5000.8 1022.49  5014.2 1023.19  5020.2 1025.72
  5035.3 1027.91  5043.2 1028.15  5050.4 1029.22  5056.3 1030.66  5115.1 1033.59
#Mann=5,-1,0
  4652.9    0.05       0  4666.4    0.12       0  4768.0    0.05       0
  4996.8    0.05       0  5000.8    0.05       0
Bank Sta=4996.8,5000.8
Exp/Cntr=0.3,0.1

Type RM Length L Ch R = 1,2447,965,965,965
BEGIN DESCRIPTION:
LITTLE LLANO 062 3.0
END DESCRIPTION:
XS GIS Cut Line= 3
      2869455.66     10257353.14      2869306.50     10257535.00
      2869205.69     10257853.11
#Sta/Elev= 30
  4764.8 1031.56  4771.9 1031.81  4792.7 1030.60  4862.2 1028.11  4899.7 1027.24
  4957.1 1023.82  4963.5 1023.94  4971.4 1022.64  4977.9 1020.51  4984.6 1019.38
  5006.5 1018.83  5006.8 1018.33  5010.3 1018.33  5010.5 1018.83  5016.5 1020.74
  5021.7 1020.71  5029.5 1022.33  5040.0 1022.95  5054.0 1022.67  5102.9 1024.01
  5118.6 1023.92  5150.9 1024.87  5156.1 1024.59  5220.7 1027.13  5247.7 1027.13
  5253.0 1027.71  5280.0 1028.98  5285.3 1028.82  5332.2 1031.26  5333.7 1031.26
#Mann=5,-1,0
  4764.8    0.12       0  4862.2    0.05       0  5006.5    0.05       0
  5010.5    0.05       0  5332.2    0.12       0
Bank Sta=5006.5,5010.5
Exp/Cntr=0.3,0.1

Type RM Length L Ch R = 1,1482,479,479,479
BEGIN DESCRIPTION:
LITTLE LLANO 062 2.0
END DESCRIPTION:
XS GIS Cut Line= 3
      2869305.72     10256953.10      2868547.25     10257179.00
      2868355.66     10257203.11
#Sta/Elev= 30
  4208.6 1032.89  4268.7 1031.32  4396.3 1027.94  4417.3 1027.79  4434.7 1026.97
  4563.4 1024.18  4590.3 1023.06  4596.9 1022.97  4644.1 1021.59  4702.6 1020.62
  4845.1 1019.47  4858.8 1020.48  4930.3 1020.18  4949.5 1019.61  4980.8 1017.21
  4991.2 1015.49  4997.6 1012.68  4997.9 1012.18  5002.0 1012.18  5002.4 1012.68
  5021.7 1013.23  5031.8 1014.03  5041.9 1015.27  5052.0 1017.48  5062.1 1018.43
  5070.0 1020.21  5092.3 1023.15  5122.5 1025.30  5155.4 1026.35  5193.1 1028.35
#Mann=7,-1,0
  4208.6    0.05       0  4268.7    0.12       0  4590.3    0.05       0
  4596.9    0.12       0  4702.6    0.05       0  4997.6    0.03       0
  5002.4    0.05       0
Bank Sta=4997.6,5002.4
Exp/Cntr=0.3,0.1

Type RM Length L Ch R = 1,1003,0,0,0
BEGIN DESCRIPTION:
LITTLE LLANO 062 1.0
END DESCRIPTION:
XS GIS Cut Line= 3
      2869105.65     10256553.12      2868509.50     10256716.00
      2868255.70     10256753.11
#Sta/Elev= 30
  4382.0 1027.60  4404.4 1027.81  4413.1 1027.07  4518.3 1024.33  4590.1 1021.64
  4713.7 1018.20  4775.5 1017.98  4807.0 1018.05  4815.2 1018.67  4827.7 1018.16
  4851.5 1018.46  4910.7 1018.08  4955.1 1016.34  4962.5 1016.08  4968.9 1013.81
  4980.8 1011.40  4981.2 1010.90  4985.3 1010.90  4985.7 1011.40  4999.4 1012.13
  5011.8 1011.57  5024.1 1012.11  5034.2 1013.16  5044.3 1016.59  5064.5 1018.63
  5074.6 1018.71  5151.6 1024.38  5156.7 1024.19  5221.5 1027.20  5256.5 1027.85
#Mann=6,-1,0
  4382.0    0.12       0  4590.1    0.05       0  4851.5    0.12       0
  4955.1    0.05       0  4980.8    0.05       0  4985.7    0.05       0
Bank Sta=4980.8,4985.7
Exp/Cntr=0.3,0.1

Chan Stop Cuts=-1