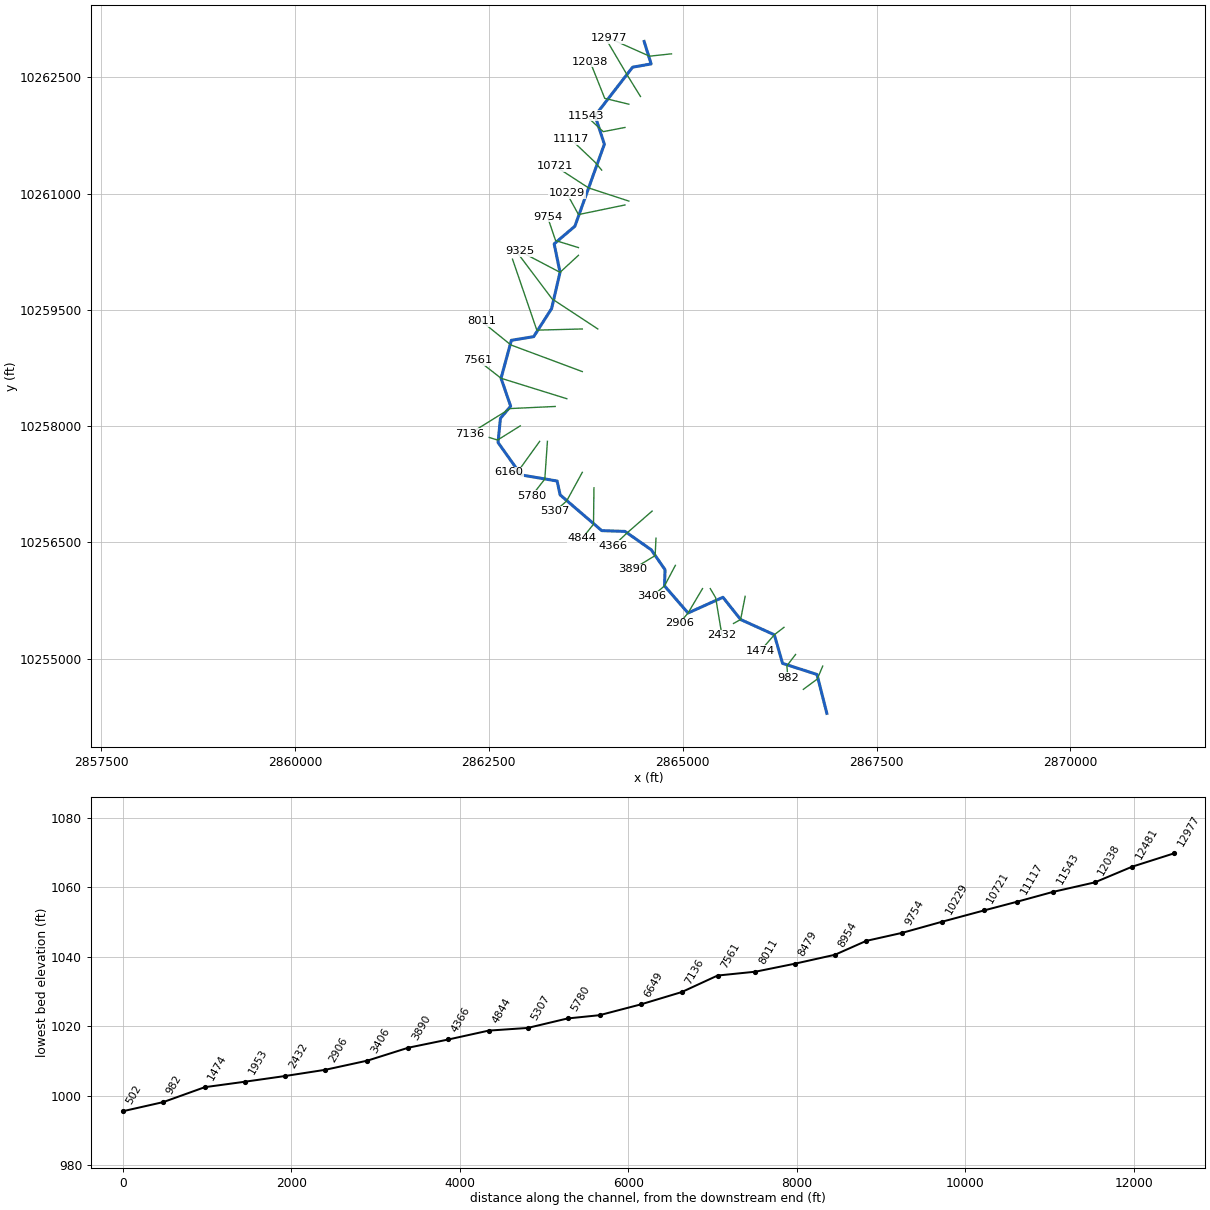
--- LITTLE LLANO 063.prj (project) ---

Proj Title=LITTLE LLANO 063 Base Level Engineering
Current Plan=p01
Default Exp/Contr=0.3,0.1
English Units
Geom File=g01
Flow File=f01
Plan File=p01
Y Axis Title=Elevation
X Axis Title(PF)=Main Channel Distance
X Axis Title(XS)=Station
BEGIN DESCRIPTION:
LITTLE LLANO 063
END DESCRIPTION:
DSS Export Rating Curves= 0
DSS Export Rating Curve Sorted= 0
DSS Export Volume Flow Curves= 0
DXF OffsetX= 0
DXF OffsetY= 0
DXF ScaleX= 1
DXF ScaleY= 10

--- LITTLE LLANO 063.p01 (plan) ---

Plan Title=Multiple Run
Short Identifier=Multiple
Geom File=g01
Flow File=f01
Subcritical Flow
K Sum by GR= 0
Std Step Tol= 0.01
Critical Tol= 0.01
Num of Std Step Trials= 20
Max Error Tol= 0.3
Flow Tol Ratio= 0.001
Split Flow NTrial= 30
Split Flow Tol= 0.02
Split Flow Ratio= 0.02
Log Output Level= 0
Friction Slope Method= 1
Unsteady Friction Slope Method= 2
Unsteady Bridges Friction Slope Method= 1
Parabolic Critical Depth
Global Vel Dist=  1 , 1 , 1
Global Log Level= 0
CheckData=True
Encroach Param= -1, 0, 0, 0
BEGIN DESCRIPTION:
Multiple Run
END DESCRIPTION:

--- LITTLE LLANO 063.f01 (steady flow) ---

Flow Title=Multiple
Number of Profiles=7
Profile Names=10-year,25-year,50-year,1pct_min,100-year,1pct_plu,500-year
River Rch & RM= LITTLE LLANO 063,Reach-1,12977
     562     934    1027     604    1190    2345    1588
Boundary for River Rch & Prof#=LITTLE LLANO 063,Reach-1,1
Up Type=0
Dn Type=3
Dn Slope=0.005
Boundary for River Rch & Prof#=LITTLE LLANO 063,Reach-1,2
Up Type=0
Dn Type=3
Dn Slope=0.005
Boundary for River Rch & Prof#=LITTLE LLANO 063,Reach-1,3
Up Type=0
Dn Type=3
Dn Slope=0.005
Boundary for River Rch & Prof#=LITTLE LLANO 063,Reach-1,4
Up Type=0
Dn Type=3
Dn Slope=0.005
Boundary for River Rch & Prof#=LITTLE LLANO 063,Reach-1,5
Up Type=0
Dn Type=3
Dn Slope=0.005
Boundary for River Rch & Prof#=LITTLE LLANO 063,Reach-1,6
Up Type=0
Dn Type=3
Dn Slope=0.005
Boundary for River Rch & Prof#=LITTLE LLANO 063,Reach-1,7
Up Type=0
Dn Type=3
Dn Slope=0.005

--- LITTLE LLANO 063.g01 (geometry) ---

Geom Title=Existing Conditions
Program Version=4.10

River Reach=LITTLE LLANO 063,Reach-1
Reach XY= 30
        2864503.       10262963.      2864592.75       10262673.
       2864354.5       10262631.        2863870.       10262005.
        2863990.       10261637.      2863609.75       10260579.
      2863342.75       10260351.      2863418.25       10259984.
       2863309.5       10259516.      2863078.25       10259154.
      2862790.75       10259107.      2862657.75       10258617.
       2862781.5       10258257.        2862650.       10258100.
        2862619.       10257788.      2862915.75       10257370.
      2863380.75       10257291.      2863419.75       10257112.
        2863956.       10256651.       2864256.5       10256641.
        2864594.       10256404.       2864772.5       10256146.
      2864765.75       10255938.        2865069.       10255588.
        2865519.       10255791.        2865747.       10255504.
       2866181.5       10255307.      2866287.75       10254938.
       2866731.5       10254795.      2866858.75       10254293.

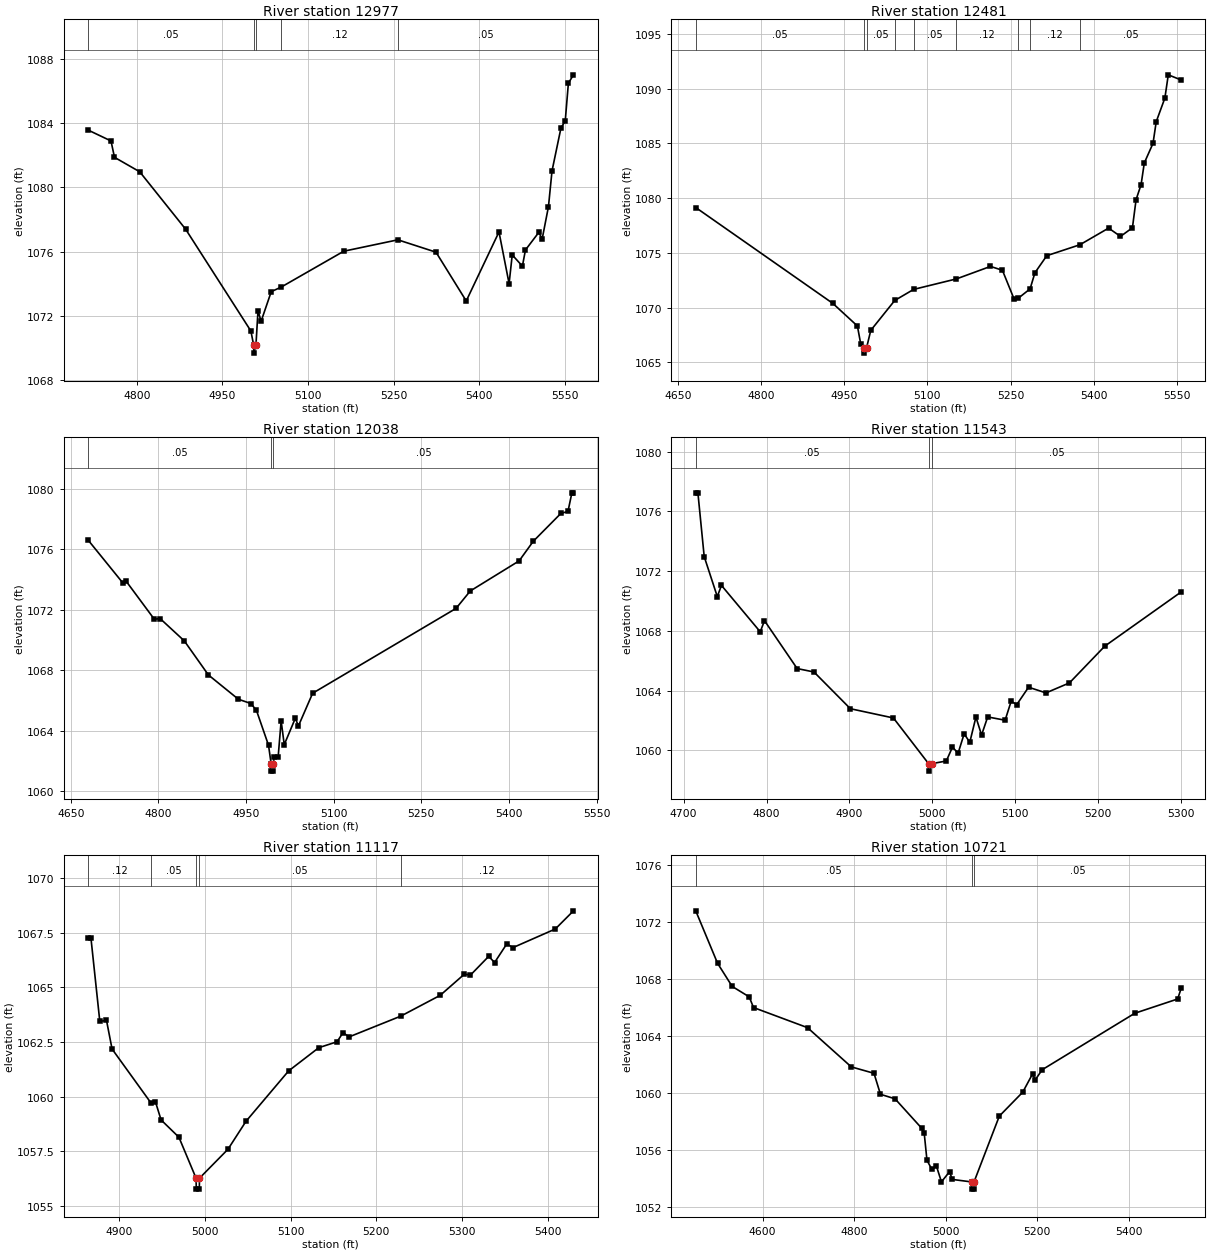
Type RM Length L Ch R = 1 ,12977   ,496,496,496
BEGIN DESCRIPTION:
LITTLE LLANO 063 28.0
END DESCRIPTION:
XS GIS Cut Line= 3
      2864855.71     10262803.11        2864572.       10262773.
      2864055.66     10263003.12
#Sta/Elev= 30
  4714.7 1083.58  4754.9  1082.9    4761 1081.88  4805.2 1080.98  4885.7  1077.4
    5000 1071.06  5004.9 1070.18  5005.2 1069.68  5008.9 1070.18  5012.5 1072.33
  5017.9 1071.66  5035.7 1073.51  5053.4  1073.8  5162.8 1076.03  5257.6 1076.74
  5324.4 1075.97  5377.4 1072.93  5434.8 1077.23  5452.5 1074.01    5458  1075.8
  5475.8  1075.1  5481.2 1076.11  5504.5  1077.2  5510.5  1076.8  5521.5 1078.81
  5527.7 1081.03  5543.4 1083.71  5550.9 1084.15  5556.4  1086.5  5565.3 1087.02
#Mann= 5 ,-1 , 0
  4714.7     .05       0  5004.9     .03       0  5008.9     .05       0
  5053.4     .12       0  5257.6     .05       0
Bank Sta=5004.9,5008.9
XS Rating Curve= 0 ,0
Exp/Cntr=0.3,0.1

Type RM Length L Ch R = 1 ,12481   ,443,443,443
BEGIN DESCRIPTION:
LITTLE LLANO 063 27.0
END DESCRIPTION:
XS GIS Cut Line= 3
       2864455.7     10262253.09       2864288.5       10262523.
      2864005.69      10263003.1
#Sta/Elev= 30
  4682.5 1079.15  4929.6 1070.39  4973.8 1068.33  4979.7 1066.72  4986.4 1066.35
  4986.6 1065.85  4990.4 1066.35  4997.9 1067.93  5041.1 1070.66  5075.1 1071.67
  5152.3 1072.63  5213.6 1073.77  5235.1 1073.42  5256.5 1070.75  5263.6 1070.86
    5285 1071.72  5293.7 1073.19  5315.1 1074.75  5374.8 1075.75  5426.5 1077.27
  5447.9 1076.51  5469.4  1077.3    5476 1079.87    5485 1081.24  5490.8 1083.22
  5506.5 1085.01  5512.3 1086.99  5527.9 1089.15    5534 1091.27  5557.2  1090.8
#Mann= 9 ,-1 , 0
  4682.5     .05       0  4986.4     .05       0  4990.4     .05       0
  5041.1     .12       0  5075.1     .05       0  5152.3     .12       0
  5263.6     .05       0    5285     .12       0  5374.8     .05       0
Bank Sta=4986.4,4990.4
XS Rating Curve= 0 ,0
Exp/Cntr=0.3,0.1

Type RM Length L Ch R = 1 ,12038   ,495,495,495
BEGIN DESCRIPTION:
LITTLE LLANO 063 26.0
END DESCRIPTION:
XS GIS Cut Line= 3
      2864305.68     10262153.11       2863994.5       10262229.
      2863805.69     10262703.09
#Sta/Elev= 30
  4679.7 1076.62  4739.7 1073.76  4744.8  1073.9  4792.9 1071.39  4803.2 1071.42
  4844.4 1069.95  4885.6  1067.7    4937 1066.09  4958.4 1065.81  4967.9 1065.35
  4988.5 1063.05  4992.9 1061.84  4993.2 1061.34  4996.7 1061.34  4996.9 1061.84
  4998.1 1062.25  5004.9 1062.25  5010.1 1064.66  5015.4 1063.09  5034.3 1064.83
  5039.7 1064.33    5064 1066.49  5309.4  1072.1  5333.7 1073.25  5417.3 1075.24
  5441.6 1076.54  5488.8 1078.38  5500.9 1078.51  5507.6 1079.74  5510.3 1079.74
#Mann= 3 ,-1 , 0
  4679.7     .05       0  4992.9     .03       0  4996.9     .05       0
Bank Sta=4992.9,4996.9
XS Rating Curve= 0 ,0
Exp/Cntr=0.3,0.1

Type RM Length L Ch R = 1 ,11543   ,426,426,426
BEGIN DESCRIPTION:
LITTLE LLANO 063 25.0
END DESCRIPTION:
XS GIS Cut Line= 3
      2864255.72     10261853.12       2863975.5       10261799.
      2863755.66     10262003.13
#Sta/Elev= 30
  4714.6 1077.25  4717.2 1077.25  4724.8 1072.98  4740.6  1070.3  4745.6 1071.05
  4792.4 1067.94  4797.5 1068.69  4836.9 1065.48  4857.2 1065.25  4901.1 1062.79
    4953 1062.17  4995.4 1059.11  4995.6 1058.61  4999.4 1059.11  5016.8 1059.29
  5024.2 1060.22    5031 1059.81  5038.3 1061.11  5045.1 1060.54  5052.5 1062.23
  5059.3 1061.03  5066.7 1062.24  5087.7 1062.02    5095 1063.29  5101.8 1063.07
    5116 1064.23    5137 1063.85  5165.3 1064.52  5207.9 1066.98    5300 1070.61
#Mann= 3 ,-1 , 0
  4714.6     .05       0  4995.4     .05       0  4999.4     .05       0
Bank Sta=4995.4,4999.4
XS Rating Curve= 0 ,0
Exp/Cntr=0.3,0.1

Type RM Length L Ch R = 1 ,11117   ,396,396,396
BEGIN DESCRIPTION:
LITTLE LLANO 063 24.0
END DESCRIPTION:
XS GIS Cut Line= 3
       2863955.7     10261303.09       2863867.5       10261407.
      2863555.69      10261703.1
#Sta/Elev= 30
  4863.7 1067.27    4867 1067.27  4877.4 1063.44  4885.2 1063.49  4891.7 1062.18
  4937.2 1059.71  4942.3 1059.77  4948.9 1058.94  4969.7 1058.15  4989.7 1056.28
    4990 1055.78  4993.5 1055.78  4993.7 1056.28  5026.9  1057.6    5048 1058.88
  5097.7 1061.18  5132.9 1062.24  5154.2 1062.51  5161.2 1062.93  5168.1 1062.73
  5228.5 1063.68  5274.5 1064.63  5302.8  1065.6  5309.7 1065.55  5331.1 1066.41
    5338 1066.13  5352.2 1066.98  5359.4 1066.81  5408.8 1067.66    5430 1068.49
#Mann= 5 ,-1 , 0
  4863.7     .12       0  4937.2     .05       0  4989.7     .05       0
  4993.7     .05       0  5228.5     .12       0
Bank Sta=4989.7,4993.7
XS Rating Curve= 0 ,0
Exp/Cntr=0.3,0.1

Type RM Length L Ch R = 1 ,10721   ,492,492,492
BEGIN DESCRIPTION:
LITTLE LLANO 063 23.0
END DESCRIPTION:
XS GIS Cut Line= 3
      2864305.65     10260903.12      2863786.75       10261073.
      2863355.67     10261353.12
#Sta/Elev= 30
    4454 1072.76  4501.7 1069.08  4533.6 1067.46  4570.7 1066.73  4580.2 1065.98
  4698.1 1064.57  4793.7 1061.82  4843.3 1061.37  4857.4  1059.9  4889.3 1059.58
  4947.7 1057.51    4953 1057.16    4959 1055.27  4969.6 1054.64  4979.6 1054.87
  4990.6 1053.76  5008.3 1054.47  5014.3 1053.93  5057.7 1053.75  5057.9 1053.25
  5061.4 1053.25  5061.7 1053.75    5117 1058.37  5168.2 1060.05  5189.5 1061.32
  5195.5 1060.91  5210.6 1061.62  5412.9 1065.58  5506.5 1066.58  5514.1 1067.32
#Mann= 3 ,-1 , 0
    4454     .05       0  5057.7     .03       0  5061.7     .05       0
Bank Sta=5057.7,5061.7
XS Rating Curve= 0 ,0
Exp/Cntr=0.3,0.1

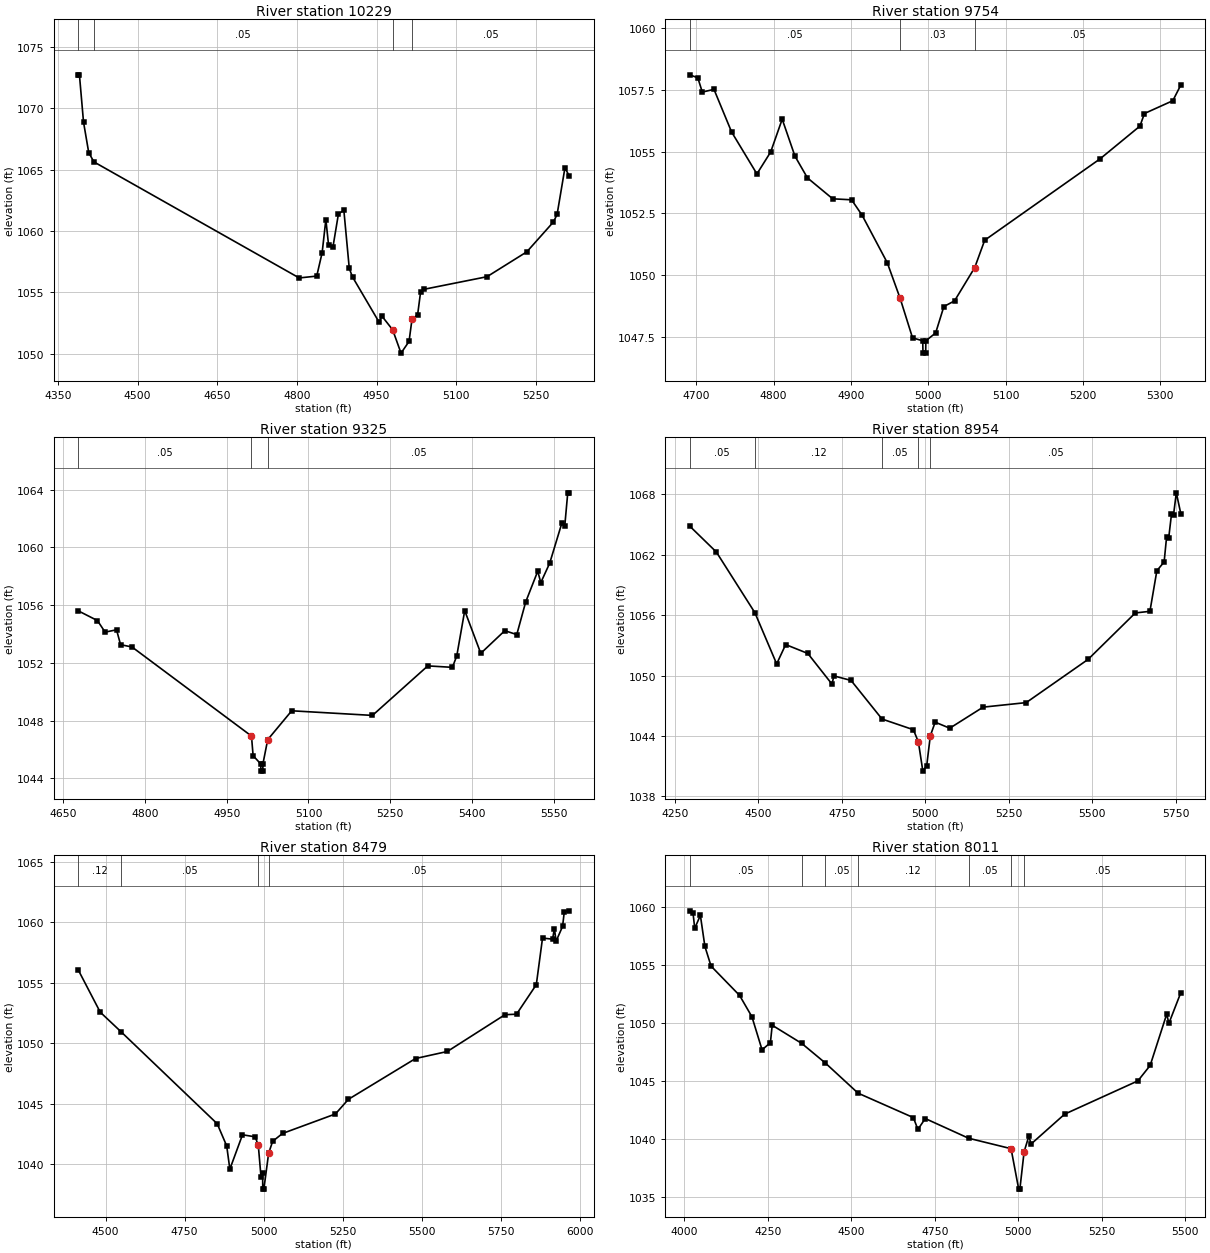
Type RM Length L Ch R = 1 ,10229   ,475,475,475
BEGIN DESCRIPTION:
LITTLE LLANO 063 22.0
END DESCRIPTION:
XS GIS Cut Line= 3
      2864255.68     10260853.11       2863656.5       10260729.
      2863505.67     10261003.14
#Sta/Elev= 30
  4388.1 1072.73  4390.6 1072.73  4398.3 1068.88  4408.1 1066.39  4417.9 1065.63
  4804.4 1056.17  4837.4 1056.32  4847.6 1058.23  4854.6 1060.93  4859.7 1058.85
  4868.1 1058.73  4878.3  1061.4  4888.5 1061.68  4898.7 1056.94  4904.8 1056.25
    4955 1052.55  4960.1 1053.06  4980.4 1051.94  4996.1 1050.04  5011.2 1050.99
  5016.9 1052.84  5027.3 1053.15    5033 1055.03  5038.9 1055.24    5158 1056.27
    5233  1058.3    5283 1060.73    5290 1061.35  5304.8 1065.16  5312.9 1064.47
#Mann= 4 ,-1 , 0
  4388.1     .12       0  4417.9     .05       0  4980.4     .03       0
  5016.9     .05       0
Bank Sta=4980.4,5016.9
XS Rating Curve= 0 ,0
Exp/Cntr=0.3,0.1

Type RM Length L Ch R = 1 ,9754    ,429,429,429
BEGIN DESCRIPTION:
LITTLE LLANO 063 21.0
END DESCRIPTION:
XS GIS Cut Line= 3
       2863655.7     10260303.11        2863361.       10260394.
      2863255.67     10260703.15
#Sta/Elev= 30
  4691.6 1058.12  4702.1    1058  4707.9 1057.42    4723 1057.53  4745.8  1055.8
  4778.5  1054.1  4796.3 1054.99  4811.2 1056.32  4827.7 1054.82  4843.8 1053.94
  4876.5 1053.09  4900.9 1053.05  4914.4 1052.43    4947  1050.5  4963.7 1049.05
  4979.7 1047.45  4992.9 1047.33  4993.2 1046.83  4996.7 1046.83  4996.9 1047.33
  5009.6 1047.65  5020.2 1048.72    5034 1048.95  5060.1  1050.3    5073 1051.41
  5222.1 1054.71  5273.7 1056.04  5279.5 1056.55  5316.2 1057.07  5326.6 1057.71
#Mann= 3 , 0 , 0
  4691.6     .05       0  4963.7     .03       0  5060.1     .05       0
Bank Sta=4963.7,5060.1
XS Rating Curve= 0 ,0
Exp/Cntr=0.3,0.1

Type RM Length L Ch R = 1 ,9325    ,371,371,371
BEGIN DESCRIPTION:
LITTLE LLANO 063 20.0
END DESCRIPTION:
XS GIS Cut Line= 3
      2863655.69     10260203.12      2863418.25       10259984.
       2862905.7      10260253.1
#Sta/Elev= 30
  4676.9 1055.61  4712.4 1054.93  4726.5 1054.13  4747.5 1054.29  4754.9 1053.26
  4775.9  1053.1  4995.3 1046.93  4998.3 1045.57  5012.3    1045  5012.6  1044.5
  5016.1  1044.5  5016.3    1045  5025.1 1046.68  5069.2 1048.68  5217.5 1048.36
  5319.1 1051.79  5364.3 1051.69  5372.3 1052.48  5386.9 1055.62  5416.4 1052.66
  5460.5 1054.23  5482.5 1053.96  5498.9 1056.22    5521 1058.35  5526.6 1057.56
    5543 1058.91  5565.1 1061.66  5570.7 1061.51  5576.1 1063.78  5578.9 1063.78
#Mann= 3 , 0 , 0
  4676.9     .05       0  4995.3     .03       0  5025.1     .05       0
Bank Sta=4995.3,5025.1
XS Rating Curve= 0 ,0
Exp/Cntr=0.3,0.1

Type RM Length L Ch R = 1 ,8954    ,475,475,475
BEGIN DESCRIPTION:
LITTLE LLANO 063 19.0
END DESCRIPTION:
XS GIS Cut Line= 3
      2863905.67     10259253.12        2863316.       10259641.
      2862855.67     10260253.13
#Sta/Elev= 30
  4294.2 1064.83    4374 1062.26  4489.6 1056.23  4554.8 1051.15  4581.8 1053.07
  4648.1 1052.19  4720.4 1049.15  4726.4 1049.96  4777.7 1049.51  4870.5 1045.68
  4964.5 1044.62  4979.5  1043.4  4992.8 1040.51  5004.4 1041.05  5015.2 1044.01
  5029.7 1045.37  5073.4 1044.77  5173.4 1046.86  5302.5 1047.31  5487.9  1051.6
  5629.5 1056.21  5673.2 1056.37    5694  1060.4  5715.8 1061.27  5723.2 1063.77
  5729.4 1063.62  5737.8 1066.01    5744 1065.96  5752.3 1068.13  5765.9 1066.04
#Mann= 5 ,-1 , 0
  4294.2     .05       0  4489.6     .12       0  4870.5     .05       0
  4979.5     .03       0  5015.2     .05       0
Bank Sta=4979.5,5015.2
XS Rating Curve= 0 ,0
Exp/Cntr=0.3,0.1

Type RM Length L Ch R = 1 ,8479    ,468,468,468
BEGIN DESCRIPTION:
LITTLE LLANO 063 18.0
END DESCRIPTION:
XS GIS Cut Line= 3
      2863705.71     10259253.11        2863119.       10259238.
      2862805.67     10260153.15
#Sta/Elev= 30
  4413.1 1056.07  4483.1 1052.56  4550.2 1050.91  4853.3 1043.34  4883.3 1041.51
  4893.3 1039.59  4933.3 1042.43  4973.3 1042.26  4983.3 1041.56    4992 1038.91
    4997 1039.31  4997.4 1037.94  5000.9 1037.94    5016  1040.9  5028.7 1041.89
    5060 1042.54  5227.4 1044.15  5268.5 1045.36    5481 1048.73  5581.4 1049.31
  5763.9 1052.35  5800.4 1052.39    5863 1054.83  5882.7 1058.68  5914.4 1058.59
  5920.3 1059.46  5925.6 1058.42  5946.1 1059.64  5951.6 1060.86  5967.3 1060.93
#Mann= 4 ,-1 , 0
  4413.1     .12       0  4550.2     .05       0  4983.3     .05       0
    5016     .05       0
Bank Sta=4983.3,5016
XS Rating Curve= 0 ,0
Exp/Cntr=0.3,0.1

Type RM Length L Ch R = 1 ,8011    ,450,450,450
BEGIN DESCRIPTION:
LITTLE LLANO 063 17.0
END DESCRIPTION:
XS GIS Cut Line= 3
      2863705.67     10258703.12      2862784.25       10259047.
      2862405.72     10259353.08
#Sta/Elev= 30
  4016.5 1059.65  4026.3  1059.5  4031.6 1058.14  4048.5 1059.26    4062 1056.58
  4080.5 1054.88  4165.9 1052.35  4202.8 1050.51  4233.1 1047.66  4258.1 1048.27
  4263.5 1049.78    4352 1048.21    4423 1046.51  4520.5 1043.92  4686.1 1041.81
  4699.6 1040.79  4721.7 1041.73  4851.5 1040.03  4978.5 1039.13  5001.4 1035.64
  5004.9 1035.64  5017.6 1038.87  5031.9 1040.22  5038.4 1039.53    5139 1042.11
  5358.2 1044.98  5394.9 1046.31  5444.5 1050.74  5450.9 1049.94  5486.8  1052.6
#Mann= 7 ,-1 , 0
  4016.5     .05       0    4352     .12       0    4423     .05       0
  4520.5     .12       0  4851.5     .05       0  4978.5     .05       0
  5017.6     .05       0
Bank Sta=4978.5,5017.6
XS Rating Curve= 0 ,0
Exp/Cntr=0.3,0.1

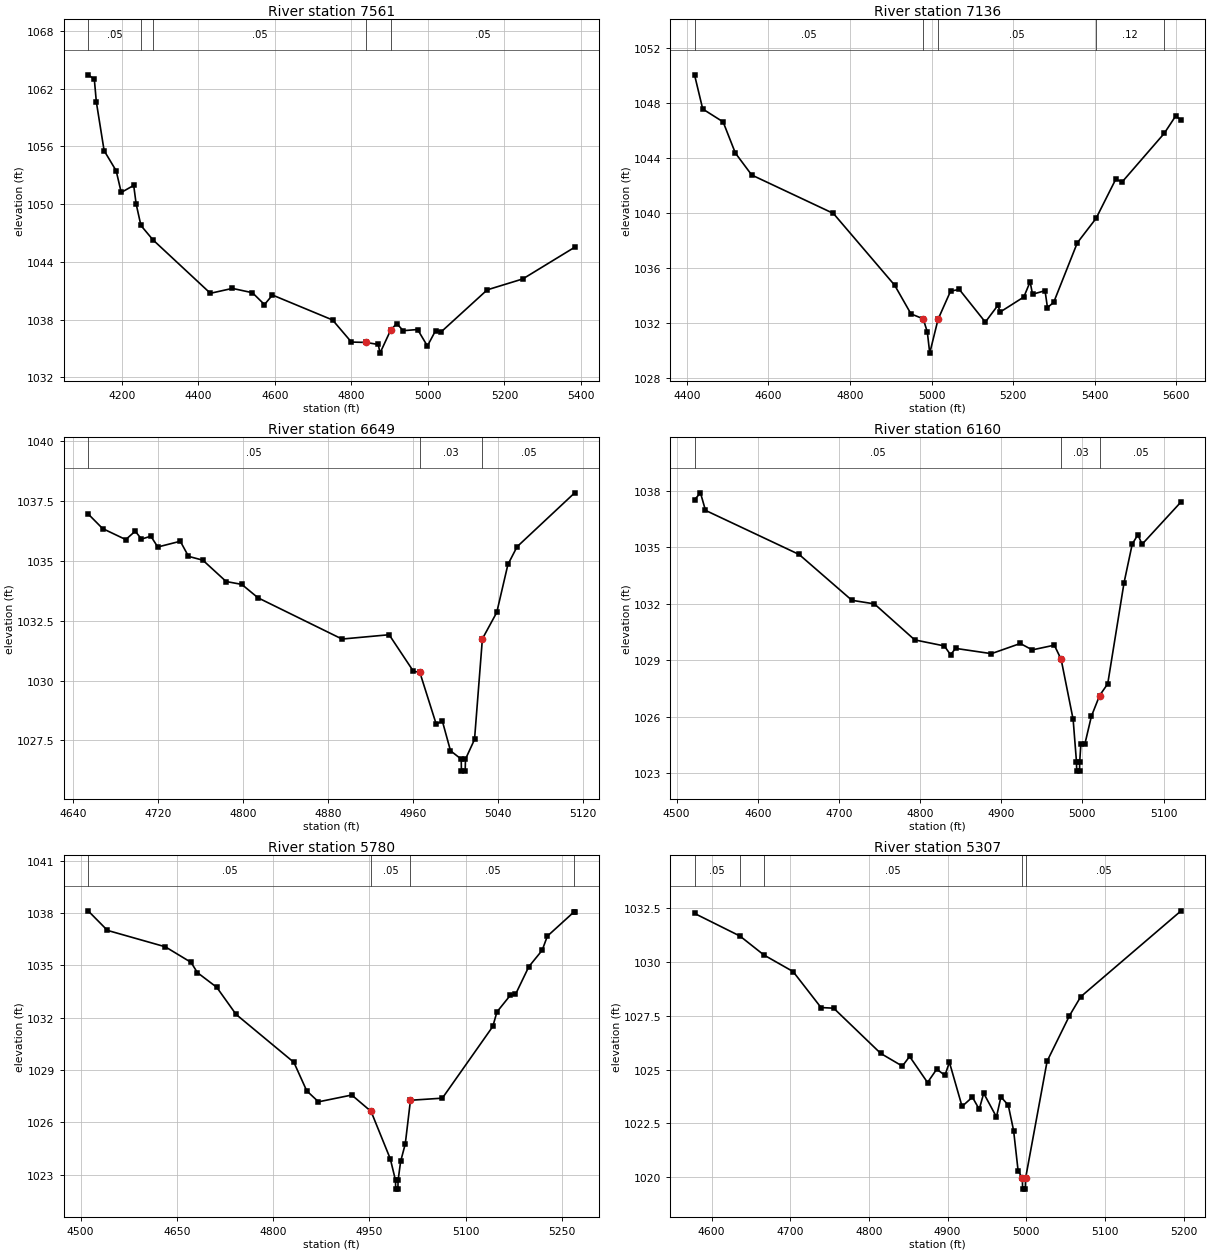
Type RM Length L Ch R = 1 ,7561    ,425,425,425
BEGIN DESCRIPTION:
LITTLE LLANO 063 16.0
END DESCRIPTION:
XS GIS Cut Line= 3
      2863505.64     10258353.13      2862657.75       10258617.
      2862355.68     10258853.11
#Sta/Elev= 30
    4112 1063.42  4128.2 1062.97  4133.5  1060.6  4153.8 1055.55  4185.3 1053.46
  4198.5 1051.21  4231.1 1051.94  4237.6 1049.99    4250 1047.78  4281.4 1046.29
  4431.5 1040.74    4489 1041.25  4541.3  1040.8  4572.8 1039.57  4593.7 1040.56
  4750.8 1037.97  4799.9 1035.68  4837.7 1035.64  4870.2 1035.43  4874.7 1034.53
  4902.7 1036.93  4918.4  1037.6  4935.3 1036.86    4973 1036.98  4998.5 1035.27
  5019.9 1036.86  5034.3 1036.73  5154.9  1041.1  5247.7 1042.23  5383.4 1045.52
#Mann= 5 ,-1 , 0
    4112     .05       0    4250     .12       0  4281.4     .05       0
  4837.7     .05       0  4902.7     .05       0
Bank Sta=4837.7,4902.7
XS Rating Curve= 0 ,0
Exp/Cntr=0.3,0.1

Type RM Length L Ch R = 1 ,7136    ,487,487,487
BEGIN DESCRIPTION:
LITTLE LLANO 063 15.0
END DESCRIPTION:
XS GIS Cut Line= 3
      2863355.72     10258253.11      2862775.25       10258226.
       2862255.7     10257903.12
#Sta/Elev= 30
  4418.9 1050.06    4439 1047.57    4489 1046.63    4519 1044.36  4559.1 1042.76
  4759.3 1039.96  4909.5 1034.73  4949.5 1032.64  4979.5 1032.28  4989.6 1031.32
  4995.5 1029.78    5016 1032.25  5046.6  1034.3    5068 1034.42  5131.8 1032.04
  5162.5 1033.26  5168.4 1032.78  5226.2 1033.87  5241.6 1034.98  5247.5 1034.07
  5278.2 1034.33  5284.1  1033.1  5299.4 1033.48  5357.3 1037.82  5403.3  1039.6
  5451.7 1042.46  5467.1 1042.25  5570.3 1045.79  5598.2 1047.05  5611.7 1046.78
#Mann= 5 ,-1 , 0
  4418.9     .05       0  4979.5     .05       0    5016     .05       0
  5403.3     .12       0  5570.3     .05       0
Bank Sta=4979.5,5016
XS Rating Curve= 0 ,0
Exp/Cntr=0.3,0.1

Type RM Length L Ch R = 1 ,6649    ,489,489,489
BEGIN DESCRIPTION:
LITTLE LLANO 063 14.0
END DESCRIPTION:
XS GIS Cut Line= 3
      2862905.72     10258003.13      2862612.75       10257820.
      2862505.65     10257853.12
#Sta/Elev= 30
  4654.5 1036.95  4668.1 1036.34  4689.9 1035.88  4698.8 1036.23  4704.7  1035.9
  4713.5 1036.02    4720 1035.57  4741.2 1035.81  4748.9 1035.18  4762.4 1035.02
  4784.3 1034.13    4799 1034.01  4814.3 1033.45  4893.3 1031.73  4937.6 1031.91
  4960.5 1030.38  4966.4 1030.35  4981.8 1028.19  4987.7  1028.3  4995.3 1027.07
  5005.4 1026.72  5005.6 1026.22  5009.1 1026.22  5009.4 1026.72  5017.9 1027.54
  5025.3 1031.74  5038.8 1032.84  5049.3 1034.84  5057.9 1035.58  5112.1 1037.83
#Mann= 3 , 0 , 0
  4654.5     .05       0  4966.4     .03       0  5025.3     .05       0
Bank Sta=4966.4,5025.3
XS Rating Curve= 0 ,0
Exp/Cntr=0.3,0.1

Type RM Length L Ch R = 1 ,6160    ,380,380,380
BEGIN DESCRIPTION:
LITTLE LLANO 063 13.0
END DESCRIPTION:
XS GIS Cut Line= 3
      2863155.66     10257803.07      2862876.75       10257415.
      2862755.73     10257403.12
#Sta/Elev= 30
  4522.1 1037.51  4529.4 1037.88  4535.6 1036.95    4651 1034.61    4716 1032.18
  4743.7 1031.99  4793.4 1030.08  4829.9 1029.76  4837.6 1029.29  4843.7 1029.63
  4887.9 1029.35  4923.5 1029.89  4938.2 1029.55  4965.4  1029.8  4973.8 1029.05
  4988.6 1025.86  4992.7 1023.62    4993 1023.12  4996.5 1023.12  4996.7 1023.62
  4998.1 1024.55    5003 1024.55  5011.1 1026.03  5021.2 1027.13  5031.2 1027.75
  5051.3 1033.11  5061.4 1035.16  5068.4 1035.66  5073.5 1035.15  5121.6  1037.4
#Mann= 3 , 0 , 0
  4522.1     .05       0  4973.8     .03       0  5021.2     .05       0
Bank Sta=4973.8,5021.2
XS Rating Curve= 0 ,0
Exp/Cntr=0.3,0.1

Type RM Length L Ch R = 1 ,5780    ,473,473,473
BEGIN DESCRIPTION:
LITTLE LLANO 063 12.0
END DESCRIPTION:
XS GIS Cut Line= 3
      2863255.69     10257803.14        2863222.       10257316.
      2863055.65     10257103.07
#Sta/Elev= 30
  4511.7 1038.12  4541.8    1037    4632 1036.06  4672.1 1035.17  4682.1 1034.58
  4712.2 1033.74  4742.3 1032.19  4832.5 1029.44  4852.5 1027.81  4870.8 1027.18
  4922.7 1027.57  4952.8 1026.63  4982.8 1023.91  4990.9 1022.68  4991.1 1022.18
  4994.6 1022.18  4994.9 1022.68  4998.9 1023.77  5006.1 1024.77  5014.2 1027.27
  5063.9 1027.39  5142.6  1031.5    5149 1032.33  5169.8 1033.28  5177.9 1033.33
  5198.7 1034.92  5219.5 1035.86  5227.6 1036.67  5269.8 1038.08  5270.2 1038.08
#Mann= 4 ,-1 , 0
  4511.7     .05       0  4952.8     .05       0  5014.2     .05       0
  5269.8     .12       0
Bank Sta=4952.8,5014.2
XS Rating Curve= 0 ,0
Exp/Cntr=0.3,0.1

Type RM Length L Ch R = 1 ,5307    ,463,463,463
BEGIN DESCRIPTION:
LITTLE LLANO 063 11.0
END DESCRIPTION:
XS GIS Cut Line= 3
      2863705.67     10257403.08       2863503.5       10257033.
      2863355.67      10256903.1
#Sta/Elev= 30
  4578.3 1032.25    4636  1031.2  4666.5 1030.32  4703.6 1029.55  4739.1 1027.88
  4755.2 1027.85    4815 1025.75  4842.5 1025.16  4851.7 1025.61  4874.5  1024.4
  4886.2 1025.02  4896.6 1024.73  4902.3 1025.34  4918.4 1023.29  4931.5 1023.72
  4940.2 1023.16  4945.9  1023.9  4962.1  1022.8  4967.8 1023.73  4977.1 1023.35
  4983.9 1022.17  4989.6 1020.31  4995.1 1019.95  4995.3 1019.45  4998.8 1019.45
  4999.1 1019.95  5026.5 1025.39  5054.9  1027.5  5069.2 1028.38  5196.8 1032.37
#Mann= 5 ,-1 , 0
  4578.3     .05       0    4636     .12       0  4666.5     .05       0
  4995.1     .05       0  4999.1     .05       0
Bank Sta=4995.1,4999.1
XS Rating Curve= 0 ,0
Exp/Cntr=0.3,0.1

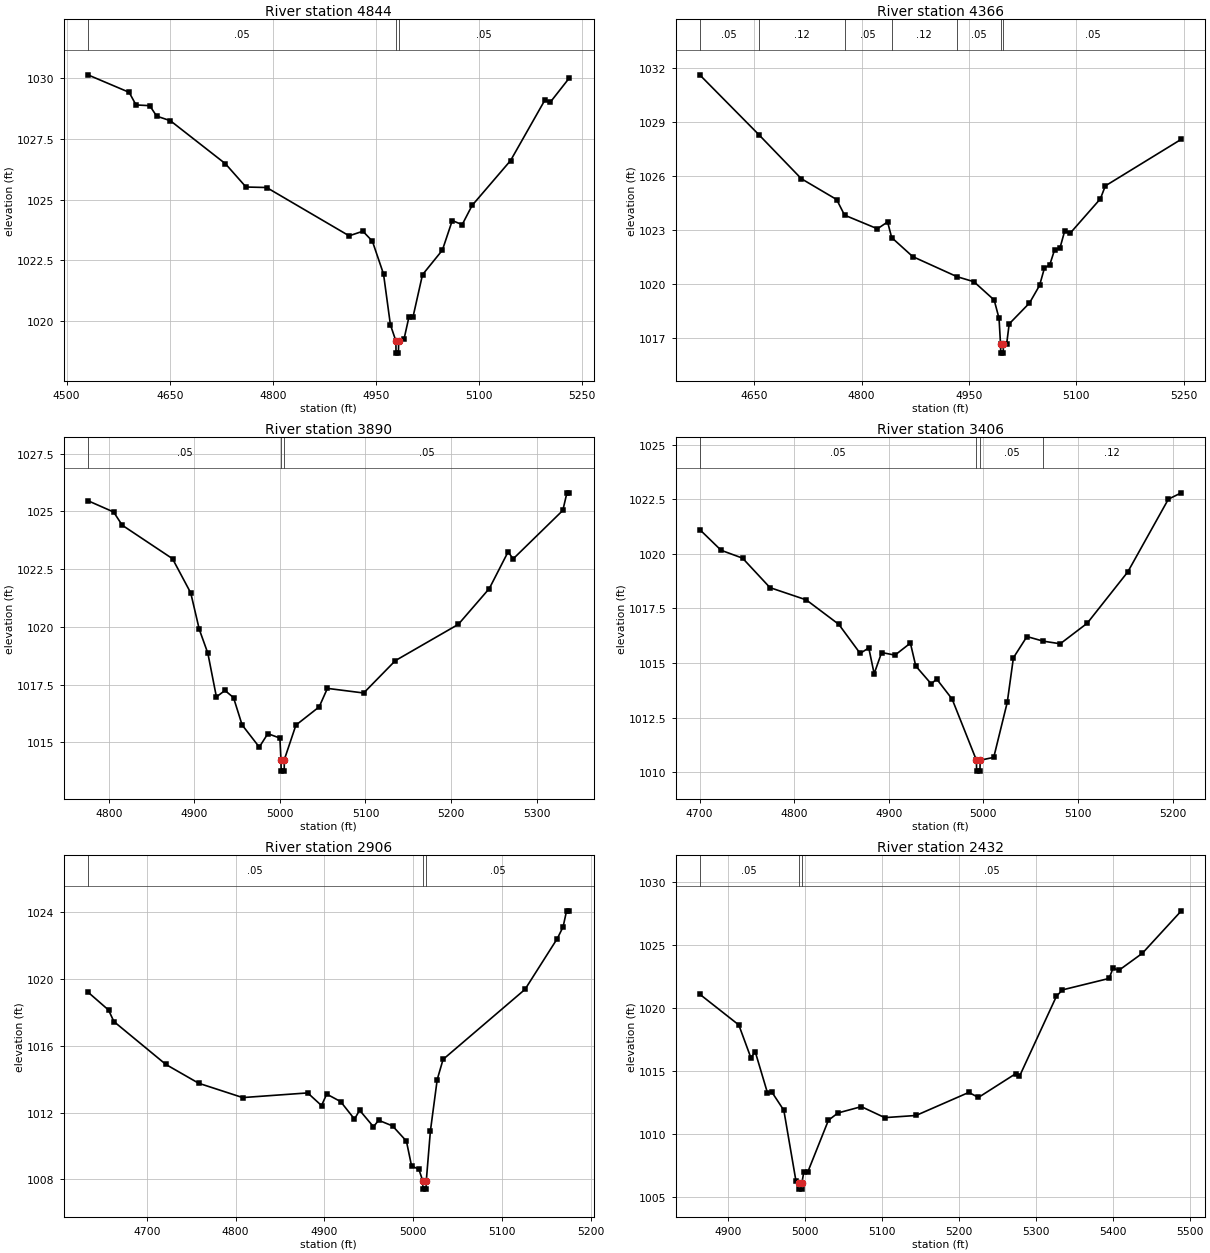
Type RM Length L Ch R = 1 ,4844    ,478,478,478
BEGIN DESCRIPTION:
LITTLE LLANO 063 10.0
END DESCRIPTION:
XS GIS Cut Line= 3
      2863855.68     10257203.07        2863850.       10256734.
      2863705.69     10256553.11
#Sta/Elev= 30
  4530.9 1030.14  4590.9 1029.42  4600.9  1028.9  4620.9 1028.87  4630.9 1028.44
  4650.9 1028.25  4730.9 1026.48  4760.9 1025.52  4790.9  1025.5  4910.9 1023.51
  4930.9  1023.7  4944.7 1023.29  4960.9 1021.94  4970.9 1019.85  4978.9 1019.18
  4979.1 1018.68  4982.6 1018.68  4982.9 1019.18  4990.9 1019.28  4997.9 1020.17
  5003.8 1020.17  5017.6 1021.91  5046.5 1022.92  5060.9 1024.14  5075.3 1023.97
  5089.7 1024.76  5145.7 1026.61  5195.4 1029.09  5203.4 1029.01  5231.4 1030.02
#Mann= 3 ,-1 , 0
  4530.9     .05       0  4978.9     .05       0  4982.9     .05       0
Bank Sta=4978.9,4982.9
XS Rating Curve= 0 ,0
Exp/Cntr=0.3,0.1

Type RM Length L Ch R = 1 ,4366    ,476,476,476
BEGIN DESCRIPTION:
LITTLE LLANO 063 9.0
END DESCRIPTION:
XS GIS Cut Line= 3
      2864605.71     10256903.13       2864284.5       10256623.
      2864105.65     10256453.08
#Sta/Elev= 30
  4573.8 1031.64  4656.3 1028.31  4715.8 1025.85  4765.1 1024.69  4776.2 1023.82
  4822.1 1023.06  4836.3 1023.44    4842 1022.57  4871.4 1021.51  4933.3 1020.39
  4956.9 1020.11  4985.2 1019.09    4992 1018.07  4994.1 1016.63  4994.4 1016.13
  4997.9 1016.13  4998.1 1016.63  5002.6 1016.63  5006.2 1017.76  5034.5 1018.92
  5048.6  1019.9  5055.5 1020.88  5062.8 1021.04  5069.7  1021.9    5077 1021.97
  5083.9 1022.96  5091.1  1022.8  5133.6 1024.73  5140.5 1025.45  5246.7 1028.05
#Mann= 7 ,-1 , 0
  4573.8     .05       0  4656.3     .12       0  4776.2     .05       0
    4842     .12       0  4933.3     .05       0  4994.1     .03       0
  4998.1     .05       0
Bank Sta=4994.1,4998.1
XS Rating Curve= 0 ,0
Exp/Cntr=0.3,0.1

Type RM Length L Ch R = 1 ,3890    ,484,484,484
BEGIN DESCRIPTION:
LITTLE LLANO 063 8.0
END DESCRIPTION:
XS GIS Cut Line= 3
      2864655.69     10256553.13      2864644.75       10256329.
      2864355.66      10256153.1
#Sta/Elev= 30
  4775.6 1025.46  4805.7 1024.97  4815.7  1024.4  4874.5 1022.95  4895.8 1021.47
  4905.8 1019.89  4915.8 1018.86  4925.8 1016.97  4935.8 1017.25  4945.8 1016.94
  4955.8 1015.76  4975.9  1014.8  4985.9 1015.38    5000 1015.19  5001.2 1014.26
  5001.5 1013.76    5005 1013.76  5005.2 1014.26  5018.7 1015.75  5045.9 1016.54
  5055.5 1017.34  5097.9 1017.14  5134.9 1018.54  5208.5 1020.11  5244.7 1021.66
  5266.7 1023.25  5272.5 1022.94  5330.6 1025.04  5335.4  1025.8  5338.4  1025.8
#Mann= 3 ,-1 , 0
  4775.6     .05       0  5001.2     .05       0  5005.2     .05       0
Bank Sta=5001.2,5005.2
XS Rating Curve= 0 ,0
Exp/Cntr=0.3,0.1

Type RM Length L Ch R = 1 ,3406    ,500,500,500
BEGIN DESCRIPTION:
LITTLE LLANO 063 7.0
END DESCRIPTION:
XS GIS Cut Line= 3
       2864905.7     10256203.13      2864765.75       10255938.
       2864605.7     10255803.13
#Sta/Elev= 30
  4700.2 1021.11  4722.8 1020.16  4745.5  1019.8  4774.5 1018.45  4812.8 1017.89
  4847.2 1016.77  4869.8 1015.44  4878.9 1015.69  4884.6 1014.51  4892.5 1015.48
  4906.6 1015.36  4922.9 1015.91  4928.6 1014.86    4945 1014.04  4950.6 1014.27
    4967 1013.35  4992.7 1010.55  4992.9 1010.05  4996.4 1010.05  4996.7 1010.55
    5011 1010.68  5025.3  1013.2  5031.8 1015.24  5046.1 1016.21  5063.3    1016
  5081.3 1015.88  5109.8 1016.82  5152.7 1019.17  5195.6  1022.5  5209.3 1022.79
#Mann= 4 ,-1 , 0
  4700.2     .05       0  4992.7     .03       0  4996.7     .05       0
  5063.3     .12       0
Bank Sta=4992.7,4996.7
XS Rating Curve= 0 ,0
Exp/Cntr=0.3,0.1

Type RM Length L Ch R = 1 ,2906    ,474,474,474
BEGIN DESCRIPTION:
LITTLE LLANO 063 6.0
END DESCRIPTION:
XS GIS Cut Line= 3
       2865255.7     10255903.15        2865069.       10255588.
      2864955.66     10255453.09
#Sta/Elev= 30
  4633.7 1019.23    4657 1018.15    4663 1017.46  4721.5 1014.89  4758.5 1013.76
  4808.1  1012.9  4881.3 1013.18  4896.9 1012.42  4902.7 1013.11  4918.4 1012.66
    4934 1011.61  4939.8 1012.14  4955.4 1011.15  4961.2 1011.54  4976.9  1011.2
  4992.5 1010.29  4998.3  1008.8  5006.5  1008.6  5010.9 1007.91  5011.2 1007.41
  5014.7 1007.41  5014.9 1007.91  5019.5 1010.89  5027.2 1013.98  5033.8 1015.19
  5126.1 1019.39  5162.5 1022.44    5169 1023.14  5172.9  1024.1  5176.2  1024.1
#Mann= 3 ,-1 , 0
  4633.7     .05       0  5010.9     .03       0  5014.9     .05       0
Bank Sta=5010.9,5014.9
XS Rating Curve= 0 ,0
Exp/Cntr=0.3,0.1

Type RM Length L Ch R = 1 ,2432    ,479,479,479
BEGIN DESCRIPTION:
LITTLE LLANO 063 5.0
END DESCRIPTION:
XS GIS Cut Line= 3
      2865355.67     10255903.13      2865425.25       10255785.
      2865505.69     10255303.07
#Sta/Elev= 30
  4862.9 1021.09  4913.7 1018.65  4929.3 1016.06  4935.1 1016.51  4950.8 1013.29
  4956.6 1013.33  4972.2 1011.88  4987.9 1006.29  4991.7 1006.13  4991.9 1005.63
  4995.4 1005.63  4995.7 1006.13  4998.2 1007.02  5003.5 1007.02  5030.1 1011.09
  5042.5 1011.67  5072.9 1012.17  5103.3  1011.3  5143.9 1011.47  5212.5  1013.3
    5225  1012.9  5273.3 1014.78  5278.3 1014.57  5326.3 1020.92  5334.1 1021.43
  5394.8 1022.34  5399.9 1023.16  5407.4 1022.98  5437.9 1024.33  5488.6  1027.7
#Mann= 3 ,-1 , 0
  4862.9     .05       0  4991.7     .03       0  4995.7     .05       0
Bank Sta=4991.7,4995.7
XS Rating Curve= 0 ,0
Exp/Cntr=0.3,0.1

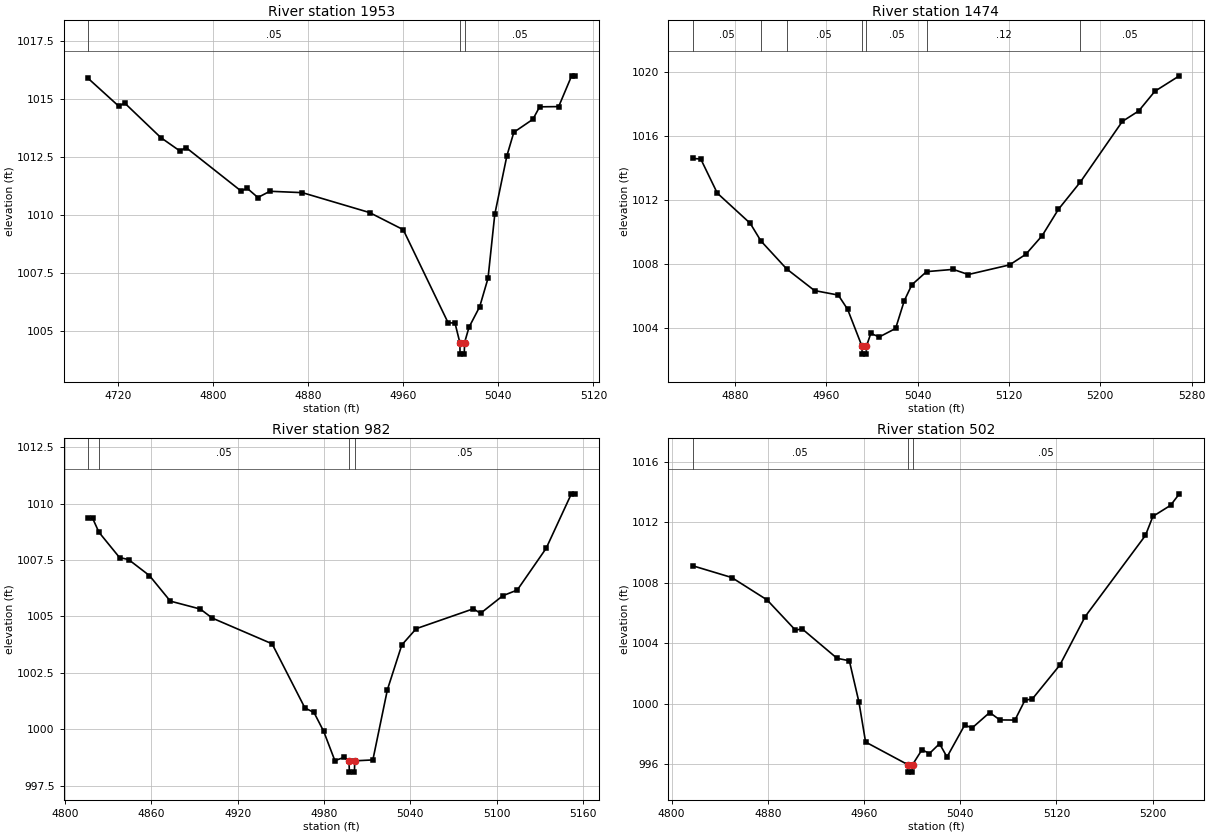
Type RM Length L Ch R = 1 ,1953    ,479,479,479
BEGIN DESCRIPTION:
LITTLE LLANO 063 4.0
END DESCRIPTION:
XS GIS Cut Line= 3
      2865805.68      10255803.1        2865747.       10255504.
      2865655.72     10255453.13
#Sta/Elev= 30
  4695.2  1015.9  4720.9  1014.7    4726 1014.83  4756.3 1013.34  4772.4 1012.76
  4777.5 1012.91  4823.8 1011.03  4828.9 1011.15  4837.9 1010.75    4848 1011.02
  4875.3 1010.96  4931.8  1010.1  4960.1 1009.36  4997.9 1005.33  5003.6 1005.33
  5007.7 1004.48  5007.9 1003.98  5011.4 1003.98  5011.7 1004.48  5015.4 1005.14
  5024.4 1006.03  5031.4 1007.26  5037.1 1010.03  5047.3 1012.56  5053.1 1013.57
  5069.1 1014.13  5074.8 1014.67  5090.8 1014.68  5101.7 1016.01  5104.5 1016.01
#Mann= 3 ,-1 , 0
  4695.2     .05       0  5007.7     .03       0  5011.7     .05       0
Bank Sta=5007.7,5011.7
XS Rating Curve= 0 ,0
Exp/Cntr=0.3,0.1

Type RM Length L Ch R = 1 ,1474    ,492,492,492
BEGIN DESCRIPTION:
LITTLE LLANO 063 3.0
END DESCRIPTION:
XS GIS Cut Line= 3
      2866305.66     10255403.09       2866181.5       10255307.
       2866005.7     10255103.13
#Sta/Elev= 30
    4843 1014.59  4850.2 1014.56  4864.7 1012.43  4893.5 1010.55  4902.9 1009.45
  4925.4 1007.71  4949.8 1006.36  4970.6 1006.08  4978.8 1005.19  4991.3  1002.9
  4991.5  1002.4    4995  1002.4  4995.3  1002.9  4999.1 1003.69  5006.5 1003.47
  5020.8    1004  5028.4 1005.73    5035 1006.72  5047.9 1007.54  5071.2 1007.68
  5084.4 1007.36  5120.6 1007.96  5134.8 1008.62  5149.1 1009.78  5163.3 1011.42
  5182.6 1013.13  5219.3  1016.9  5233.6 1017.55  5247.8 1018.78  5269.2 1019.74
#Mann= 7 ,-1 , 0
    4843     .05       0  4902.9     .12       0  4925.4     .05       0
  4991.3     .05       0  4995.3     .05       0  5047.9     .12       0
  5182.6     .05       0
Bank Sta=4991.3,4995.3
XS Rating Curve= 0 ,0
Exp/Cntr=0.3,0.1

Type RM Length L Ch R = 1 ,982     ,480,480,480
BEGIN DESCRIPTION:
LITTLE LLANO 063 2.0
END DESCRIPTION:
XS GIS Cut Line= 3
      2866455.68     10255053.11        2866344.       10254907.
      2866355.68     10254753.14
#Sta/Elev= 30
  4816.1 1009.35  4819.2 1009.35  4823.6 1008.73  4837.9 1007.61  4844.2 1007.52
  4858.7 1006.81  4873.2 1005.68    4894 1005.33  4902.3 1004.93  4943.9 1003.79
  4966.7 1000.95    4973 1000.75  4979.7  999.92  4987.5  998.62  4993.8  998.76
  4997.3  998.61  4997.6  998.11  5001.1  998.11  5001.3  998.61  5013.9  998.65
    5024 1001.76    5034 1003.74    5044 1004.46  5083.7 1005.34  5088.7 1005.14
  5104.2 1005.92  5114.2 1006.17  5134.3 1008.02  5151.8 1010.43  5154.3 1010.43
#Mann= 4 ,-1 , 0
  4816.1     .12       0  4823.6     .05       0  4997.3     .03       0
  5001.3     .05       0
Bank Sta=4997.3,5001.3
XS Rating Curve= 0 ,0
Exp/Cntr=0.3,0.1

Type RM Length L Ch R = 1 ,502     ,0,0,0
BEGIN DESCRIPTION:
LITTLE LLANO 063 1.0
END DESCRIPTION:
XS GIS Cut Line= 3
       2866805.7     10254903.15       2866734.5       10254735.
      2866555.68     10254603.11
#Sta/Elev= 30
  4817.4 1009.12    4850 1008.34  4879.4 1006.86    4903 1004.86  4908.5 1004.95
  4937.6    1003  4947.8 1002.84  4955.8  1000.1  4961.3  997.47  4996.3  995.98
  4996.5  995.48  5000.1  995.48  5000.4  995.98  5008.2  996.96  5014.4  996.71
  5022.8  997.36    5029  996.48  5043.7  998.59  5049.9   998.4  5064.5  999.42
  5072.9  998.93  5085.5  998.92  5093.8 1000.23    5100 1000.32  5122.8 1002.55
  5143.9 1005.76    5194 1011.12  5200.2 1012.38  5214.9 1013.11  5222.2 1013.87
#Mann= 3 ,-1 , 0
  4817.4     .05       0  4996.3     .03       0  5000.4     .05       0
Bank Sta=4996.3,5000.4
XS Rating Curve= 0 ,0
Exp/Cntr=0.3,0.1

Chan Stop Cuts=-1
Use User Specified Reach Order=0
Composite Channel Slope=5