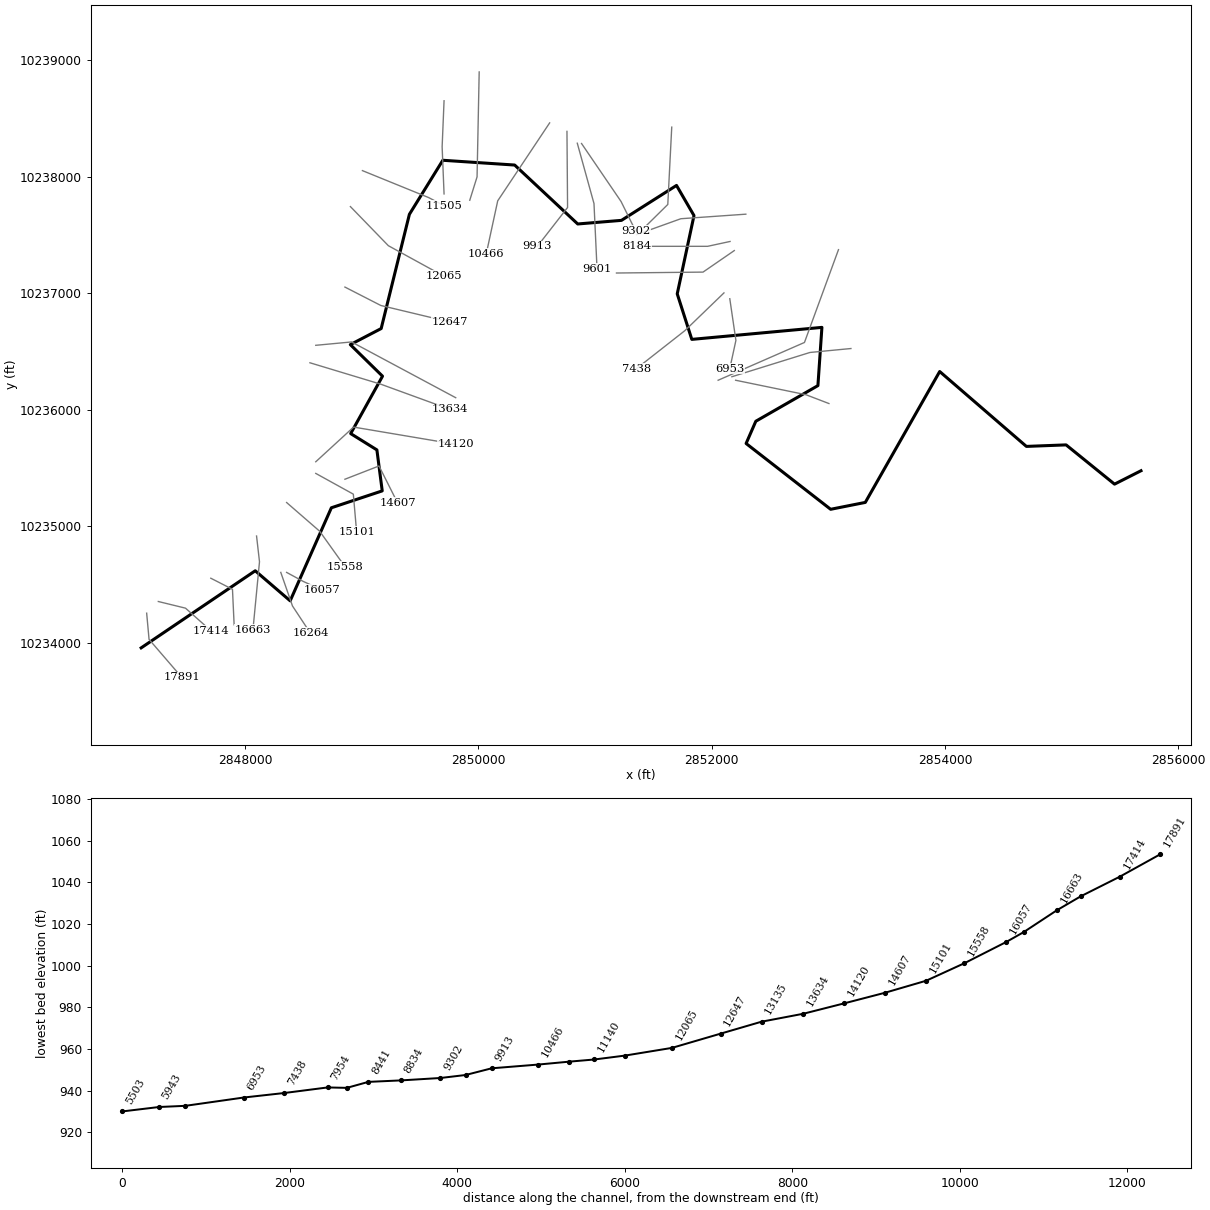
--- LITTLE LLANO 065.prj (project) ---

Proj Title=LITTLE LLANO 065 Base Level Engineering
Current Plan=p01
Default Exp/Contr=0.3,0.1
English Units
Geom File=g01
Flow File=f01
Plan File=p01
BEGIN DESCRIPTION:
LITTLE LLANO 065
END DESCRIPTION:

--- LITTLE LLANO 065.p01 (plan) ---

Plan Title=Multiple Run
Short Identifier=Multiple
Geom File=g01
Flow File=f01
Subcritical Flow
K Sum by GR= 0
Std Step Tol= 0.01
Critical Tol= 0.01
Num of Std Step Trials= 20
Max Error Tol= 0.3
Flow Tol Ratio= 0.001
Split Flow NTrial= 30
Split Flow Tol= 0.02
Split Flow Ratio= 0.02
Log Output Level= 0
Friction Slope Method= 1
Unsteady Friction Slope Method= 2
Unsteady Bridges Friction Slope Method= 1
Parabolic Critical Depth
Global Vel Dist=  1 , 1 , 1
Global Log Level= 0
CheckData=True
Encroach Param= -1, 0, 0, 0
BEGIN DESCRIPTION:
Multiple Run
END DESCRIPTION:

--- LITTLE LLANO 065.f01 (steady flow) ---

Flow Title=Multiple
Number of Profiles=7
Profile Names=10-year,25-year,50-year,1pct_min,100-year,1pct_plu,500-year
River Rch & RM= LITTLE LLANO 065,Reach-1,17891
     877    1494    2276    1597    3156    6237    4404
River Rch & RM= LITTLE LLANO 065,Reach-1,11140
    1473    2581    4159    2907    5866   11837    8121
River Rch & RM= LITTLE LLANO 065,Reach-1,4515
    1678    2967    4786    3313    6777   13862    9369
River Rch & RM= LITTLE LLANO 065,Reach-1,1618
    1743    3094    5042    3469    7162   14788    9928
Boundary for River Rch & Prof#=LITTLE LLANO 065,Reach-1,1
Up Type=0
Dn Type=3
Dn Slope=0.005
Boundary for River Rch & Prof#=LITTLE LLANO 065,Reach-1,2
Up Type=0
Dn Type=3
Dn Slope=0.005
Boundary for River Rch & Prof#=LITTLE LLANO 065,Reach-1,3
Up Type=0
Dn Type=3
Dn Slope=0.005
Boundary for River Rch & Prof#=LITTLE LLANO 065,Reach-1,4
Up Type=0
Dn Type=3
Dn Slope=0.005
Boundary for River Rch & Prof#=LITTLE LLANO 065,Reach-1,5
Up Type=0
Dn Type=3
Dn Slope=0.005
Boundary for River Rch & Prof#=LITTLE LLANO 065,Reach-1,6
Up Type=0
Dn Type=3
Dn Slope=0.005
Boundary for River Rch & Prof#=LITTLE LLANO 065,Reach-1,7
Up Type=0
Dn Type=3
Dn Slope=0.005

--- LITTLE LLANO 065.g01 (geometry) ---

Geom Title=Existing Conditions

River Reach=LITTLE LLANO 065,Reach-1
Reach XY= 30
      2847108.50     10233955.00      2848086.75     10234617.00
      2848386.25     10234359.00      2848739.50     10235158.00
      2849175.50     10235303.00      2849129.75     10235655.00
      2848905.00     10235795.00      2849178.00     10236288.00
      2848902.00     10236559.00      2849166.50     10236697.00
      2849408.50     10237678.00      2849695.00     10238142.00
      2850311.25     10238101.00      2850851.75     10237595.00
      2851226.75     10237626.00      2851698.75     10237926.00
      2851848.75     10237667.00      2851705.00     10236995.00
      2851830.00     10236604.00      2852945.50     10236707.00
      2852911.25     10236207.00      2852378.75     10235901.00
      2852295.50     10235710.00      2853020.50     10235145.00
      2853317.50     10235204.00      2853955.50     10236328.00
      2854698.75     10235685.00      2855039.25     10235698.00
      2855454.50     10235361.00      2855681.50     10235476.00

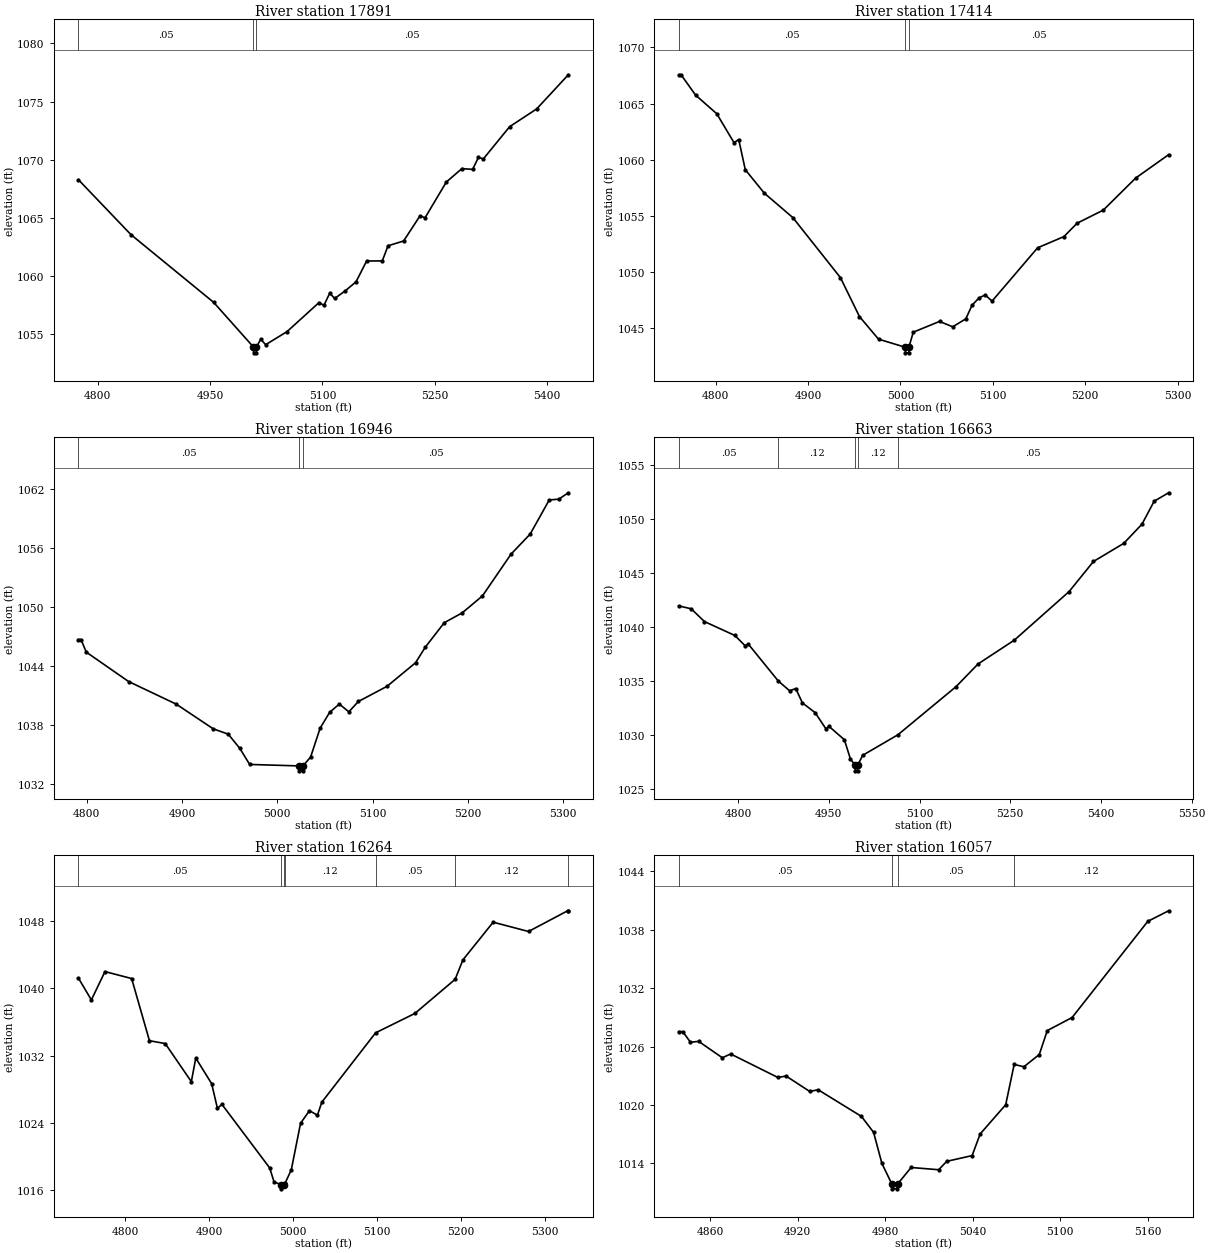
Type RM Length L Ch R = 1,17891,477,477,477
BEGIN DESCRIPTION:
LITTLE LLANO 065 36.0
END DESCRIPTION:
XS GIS Cut Line= 3
      2847155.69     10234253.06      2847176.25     10234028.00
      2847455.67     10233703.13
#Sta/Elev= 30
  4774.0 1068.29  4844.2 1063.57  4954.7 1057.75  5007.9 1053.91  5008.2 1053.41
  5011.7 1053.41  5011.9 1053.91  5017.6 1054.58  5024.2 1054.11  5052.7 1055.23
  5095.5 1057.73  5102.1 1057.49  5109.8 1058.54  5116.4 1058.08  5130.6 1058.74
  5144.9 1059.51  5159.1 1061.30  5180.0 1061.31  5187.7 1062.61  5208.5 1063.02
  5230.5 1065.19  5237.1 1065.01  5265.6 1068.09  5286.4 1069.24  5300.7 1069.17
  5308.4 1070.20  5315.0 1070.07  5350.1 1072.84  5386.3 1074.37  5428.5 1077.30
#Mann=3,-1,0
  4774.0    0.05       0  5007.9    0.05       0  5011.9    0.05       0
Bank Sta=5007.9,5011.9
Exp/Cntr=0.3,0.1

Type RM Length L Ch R = 1,17414,468,468,468
BEGIN DESCRIPTION:
LITTLE LLANO 065 35.0
END DESCRIPTION:
XS GIS Cut Line= 3
      2847255.65     10234353.12      2847488.75     10234296.00
      2847705.69     10234103.10
#Sta/Elev= 30
  4760.0 1067.56  4762.6 1067.56  4778.3 1065.75  4801.2 1064.09  4819.9 1061.51
  4825.0 1061.79  4832.1 1059.10  4852.7 1057.01  4883.6 1054.83  4935.1 1049.48
  4955.7 1046.01  4976.3 1044.00  5005.2 1043.28  5005.5 1042.78  5009.0 1042.78
  5009.2 1043.28  5013.9 1044.62  5042.4 1045.58  5056.6 1045.10  5070.8 1045.81
  5077.5 1047.02  5085.0 1047.67  5091.7 1047.94  5099.2 1047.39  5148.5 1052.14
  5177.0 1053.14  5191.2 1054.33  5219.6 1055.50  5254.7 1058.36  5290.3 1060.44
#Mann=3,-1,0
  4760.0    0.05       0  5005.2    0.03       0  5009.2    0.05       0
Bank Sta=5005.2,5009.2
Exp/Cntr=0.3,0.1

Type RM Length L Ch R = 1,16946,283,283,283
BEGIN DESCRIPTION:
LITTLE LLANO 065 34.0
END DESCRIPTION:
XS GIS Cut Line= 3
      2847705.72     10234553.09      2847891.50     10234458.00
      2847905.68     10234153.13
#Sta/Elev= 30
  4791.3 1046.67  4794.1 1046.67  4799.6 1045.39  4844.0 1042.40  4894.0 1040.10
  4932.8 1037.59  4948.5 1037.05  4960.6 1035.61  4971.0 1033.97  5022.9 1033.82
  5023.2 1033.32  5026.7 1033.32  5026.9 1033.82  5034.9 1034.72  5044.9 1037.66
  5054.9 1039.27  5065.0 1040.11  5075.0 1039.32  5085.0 1040.37  5115.0 1041.91
  5145.0 1044.31  5155.1 1045.88  5175.1 1048.38  5193.9 1049.38  5215.1 1051.10
  5245.2 1055.36  5265.2 1057.39  5285.2 1060.86  5295.2 1060.94  5305.2 1061.59
#Mann=3,-1,0
  4791.3    0.05       0  5022.9    0.05       0  5026.9    0.05       0
Bank Sta=5022.9,5026.9
Exp/Cntr=0.3,0.1

Type RM Length L Ch R = 1,16663,399,399,399
BEGIN DESCRIPTION:
Mapping XS 91caf160
END DESCRIPTION:
XS GIS Cut Line= 3
      2848097.96     10234915.43      2848123.15     10234694.53
      2848066.96     10234109.35
#Sta/Elev= 30
  4701.7 1041.94  4722.4 1041.67  4744.3 1040.49  4794.6 1039.20  4811.8 1038.24
  4816.9 1038.40  4866.5 1034.98  4885.2 1034.08  4895.3 1034.29  4906.3 1032.96
  4927.3 1032.06  4945.2 1030.56  4950.2 1030.79  4975.7 1029.55  4985.7 1027.77
  4993.8 1027.17  4994.0 1026.67  4997.5 1026.67  4997.8 1027.17  5005.8 1028.10
  5064.3 1030.01  5160.3 1034.46  5196.7 1036.56  5257.0 1038.78  5347.4 1043.27
  5387.6 1046.05  5437.8 1047.73  5467.9 1049.51  5488.0 1051.63  5511.9 1052.41
#Mann=5,-1,0
  4701.7    0.05       0  4866.5    0.12       0  4993.8    0.07       0
  4997.8    0.12       0  5064.3    0.05       0
Bank Sta=4993.8,4997.8
Exp/Cntr=0.3,0.1

Type RM Length L Ch R = 1,16264,207,207,207
BEGIN DESCRIPTION:
LITTLE LLANO 065 33.0
END DESCRIPTION:
XS GIS Cut Line= 3
      2848305.69     10234603.08      2848406.06     10234314.74
      2848559.14     10234082.22
#Sta/Elev= 30
  4744.5 1041.25  4760.0 1038.63  4776.2 1042.01  4808.0 1041.18  4829.2 1033.77
  4848.0 1033.43  4879.1 1028.89  4884.4 1031.70  4903.3 1028.65  4910.2 1025.70
  4915.5 1026.19  4972.4 1018.61  4977.7 1016.93  4986.0 1016.61  4986.3 1016.11
  4990.0 1016.61  4991.0 1016.83  4998.2 1018.38  5009.2 1023.92  5019.8 1025.43
  5029.3 1024.89  5034.6 1026.45  5098.6 1034.71  5145.4 1037.02  5193.4 1041.09
  5202.6 1043.40  5238.7 1047.90  5280.8 1046.79  5327.4 1049.26  5328.2 1049.26
#Mann=7,-1,0
  4744.5    0.05       0  4986.0    0.07       0  4990.0    0.05       0
  4991.0    0.12       0  5098.6    0.05       0  5193.4    0.12       0
  5327.4    0.05       0
Bank Sta=4986,4990
Exp/Cntr=0.3,0.1

Type RM Length L Ch R = 1,16057,499,499,499
BEGIN DESCRIPTION:
LITTLE LLANO 065 32.0
END DESCRIPTION:
XS GIS Cut Line= 3
      2848355.71     10234603.10      2848497.50     10234526.00
      2848655.71     10234453.10
#Sta/Elev= 30
  4838.6 1027.53  4841.4 1027.53  4846.7 1026.44  4852.3 1026.53  4868.5 1024.85
  4874.2 1025.24  4906.5 1022.83  4912.2 1022.97  4928.4 1021.39  4934.1 1021.57
  4963.8 1018.83  4972.1 1017.20  4977.8 1014.01  4984.6 1011.90  4984.8 1011.40
  4988.3 1011.40  4988.6 1011.90  4997.8 1013.59  5016.7 1013.36  5022.2 1014.22
  5039.6 1014.81  5045.1 1017.03  5062.6 1020.03  5068.4 1024.16  5075.1 1023.93
  5085.6 1025.18  5091.1 1027.64  5108.1 1028.98  5159.9 1038.84  5174.2 1039.93
#Mann=4,-1,0
  4838.6    0.05       0  4984.6    0.05       0  4988.6    0.05       0
  5068.4    0.12       0
Bank Sta=4984.6,4988.6
Exp/Cntr=0.3,0.1

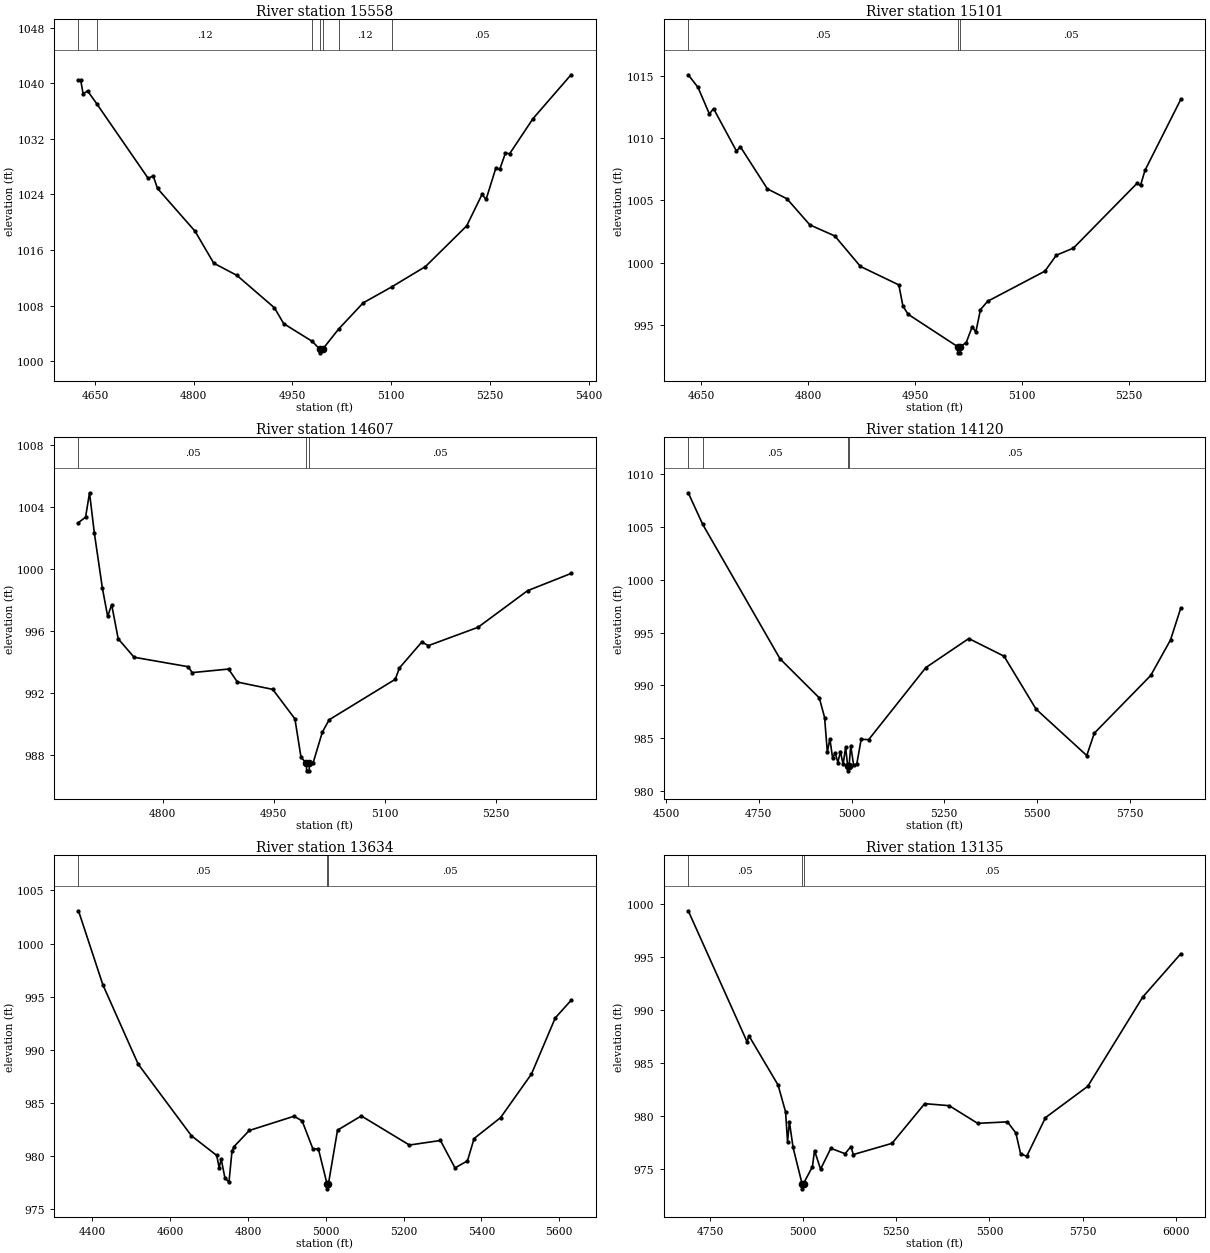
Type RM Length L Ch R = 1,15558,457,457,457
BEGIN DESCRIPTION:
LITTLE LLANO 065 31.0
END DESCRIPTION:
XS GIS Cut Line= 3
      2848355.68     10235203.11      2848638.75     10234957.00
      2848855.70     10234653.09
#Sta/Elev= 30
  4624.9 1040.46  4628.2 1040.46  4632.0 1038.48  4638.7 1038.91  4652.8 1037.04
  4730.9 1026.31  4738.4 1026.69  4745.0 1024.87  4802.0 1018.72  4830.5 1014.11
  4865.6 1012.36  4922.6 1007.70  4936.8 1005.41  4980.3 1002.85  4991.8 1001.71
  4992.1 1001.21  4995.8 1001.71  5020.1 1004.62  5057.5 1008.40  5100.9 1010.70
  5152.2 1013.63  5214.8 1019.48  5238.2 1024.02  5244.3 1023.29  5259.1 1027.79
  5265.2 1027.66  5273.8 1029.98  5280.0 1029.85  5315.6 1034.92  5373.4 1041.23
#Mann=7,-1,0
  4624.9    0.05       0  4652.8    0.12       0  4980.3    0.05       0
  4991.8    0.03       0  4995.8    0.05       0  5020.1    0.12       0
  5100.9    0.05       0
Bank Sta=4991.8,4995.8
Exp/Cntr=0.3,0.1

Type RM Length L Ch R = 1,15101,494,494,494
BEGIN DESCRIPTION:
LITTLE LLANO 065 30.0
END DESCRIPTION:
XS GIS Cut Line= 3
      2848605.72     10235453.09      2848927.75     10235275.00
      2848955.68     10234953.11
#Sta/Elev= 30
  4632.0 1015.06  4645.7 1014.05  4661.7 1011.92  4667.5 1012.35  4699.6 1008.96
  4705.3 1009.28  4743.1 1005.92  4770.5 1005.13  4802.6 1003.04  4837.7 1002.15
  4873.6  999.71  4927.5  998.23  4933.2  996.54  4940.5  995.88  5009.9  993.29
  5010.2  992.79  5013.7  992.79  5013.9  993.29  5022.0  993.61  5030.5  994.89
  5035.5  994.45  5042.0  996.25  5052.1  996.92  5132.4  999.33  5148.5 1000.61
  5172.5 1001.18  5261.6 1006.36  5266.6 1006.20  5272.9 1007.41  5323.1 1013.09
#Mann=3,-1,0
  4632.0    0.05       0  5009.9    0.03       0  5013.9    0.05       0
Bank Sta=5009.9,5013.9
Exp/Cntr=0.3,0.1

Type RM Length L Ch R = 1,14607,487,487,487
BEGIN DESCRIPTION:
LITTLE LLANO 065 29.0
END DESCRIPTION:
XS GIS Cut Line= 3
      2848855.70     10235403.12      2849148.00     10235517.00
      2849305.70     10235203.08
#Sta/Elev= 30
  4686.3 1002.99  4695.9 1003.34  4701.2 1004.91  4707.7 1002.32  4718.5  998.79
  4725.7  996.94  4731.1  997.70  4739.9  995.50  4761.4  994.31  4834.5  993.70
  4839.8  993.32  4888.9  993.55  4900.9  992.71  4948.6  992.24  4978.5  990.34
  4986.8  987.85  4994.1  987.49  4994.3  986.99  4997.8  986.99  4998.1  987.49
  5003.0  987.49  5015.5  989.48  5024.7  990.28  5114.0  992.89  5119.6  993.62
  5149.8  995.29  5158.7  995.06  5225.7  996.24  5292.6  998.60  5351.3  999.71
#Mann=3,-1,0
  4686.3    0.05       0  4994.1    0.05       0  4998.1    0.05       0
Bank Sta=4994.1,4998.1
Exp/Cntr=0.3,0.1

Type RM Length L Ch R = 1,14120,486,486,486
BEGIN DESCRIPTION:
LITTLE LLANO 065 28.0
END DESCRIPTION:
XS GIS Cut Line= 3
      2848605.66     10235553.09      2848930.00     10235851.00
      2849805.70     10235703.11
#Sta/Elev= 30
  4559.6 1008.26  4598.7 1005.26  4807.2  992.52  4913.2  988.81  4927.4  986.95
  4934.8  983.65  4941.6  984.95  4949.0  983.10  4955.8  983.62  4963.2  982.69
  4970.0  983.73  4977.4  982.52  4984.1  984.14  4989.5  982.40  4989.8  981.90
  4993.5  982.40  4997.9  984.28  5005.8  982.41  5014.1  982.53  5026.0  984.89
  5046.3  984.86  5200.5  991.69  5316.3  994.44  5411.4  992.77  5497.7  987.75
  5634.5  983.35  5654.8  985.47  5807.0  990.94  5860.4  994.31  5888.1  997.34
#Mann=4,-1,0
  4559.6    0.12       0  4598.7    0.05       0  4989.5    0.03       0
  4993.5    0.05       0
Bank Sta=4989.5,4993.5
Exp/Cntr=0.3,0.1

Type RM Length L Ch R = 1,13634,499,499,499
BEGIN DESCRIPTION:
LITTLE LLANO 065 27.0
END DESCRIPTION:
XS GIS Cut Line= 3
      2848555.71     10236403.10      2849163.75     10236219.00
      2849755.71     10236003.10
#Sta/Elev= 30
  4364.7 1003.09  4427.4  996.12  4518.1  988.66  4655.0  981.92  4719.9  980.07
  4726.1  978.92  4731.3  979.74  4740.8  977.97  4751.3  977.55  4759.0  980.45
  4764.2  980.90  4803.5  982.42  4918.4  983.76  4939.3  983.32  4967.0  980.68
  4981.1  980.68  5003.0  977.43  5003.2  976.93  5007.0  977.43  5030.2  982.45
  5091.3  983.79  5214.9  981.05  5294.6  981.48  5332.0  978.90  5364.0  979.56
  5381.0  981.66  5449.1  983.63  5528.4  987.73  5589.6  993.01  5630.1  994.66
#Mann=3,-1,0
  4364.7    0.05       0  5003.0    0.03       0  5007.0    0.05       0
Bank Sta=5003,5007
Exp/Cntr=0.3,0.1

Type RM Length L Ch R = 1,13135,488,488,488
BEGIN DESCRIPTION:
LITTLE LLANO 065 26.0
END DESCRIPTION:
XS GIS Cut Line= 3
      2848605.66     10236553.11      2848912.50     10236582.00
      2849805.71     10236103.10
#Sta/Elev= 30
  4691.8  999.39  4849.7  987.01  4854.7  987.57  4932.9  982.92  4953.0  980.38
  4958.3  977.55  4963.3  979.44  4973.1  977.02  4997.1  973.61  4997.3  973.11
  5001.1  973.61  5025.0  975.20  5030.7  976.72  5046.9  974.97  5074.5  976.94
  5112.7  976.43  5128.4  977.11  5134.7  976.35  5238.6  977.41  5326.3  981.16
  5392.1  980.97  5468.5  979.30  5548.3  979.44  5570.9  978.39  5583.8  976.41
  5600.1  976.19  5650.4  979.84  5763.8  982.80  5911.3  991.23  6013.5  995.33
#Mann=3,-1,0
  4691.8    0.05       0  4997.1    0.05       0  5001.1    0.05       0
Bank Sta=4997.1,5001.1
Exp/Cntr=0.3,0.1

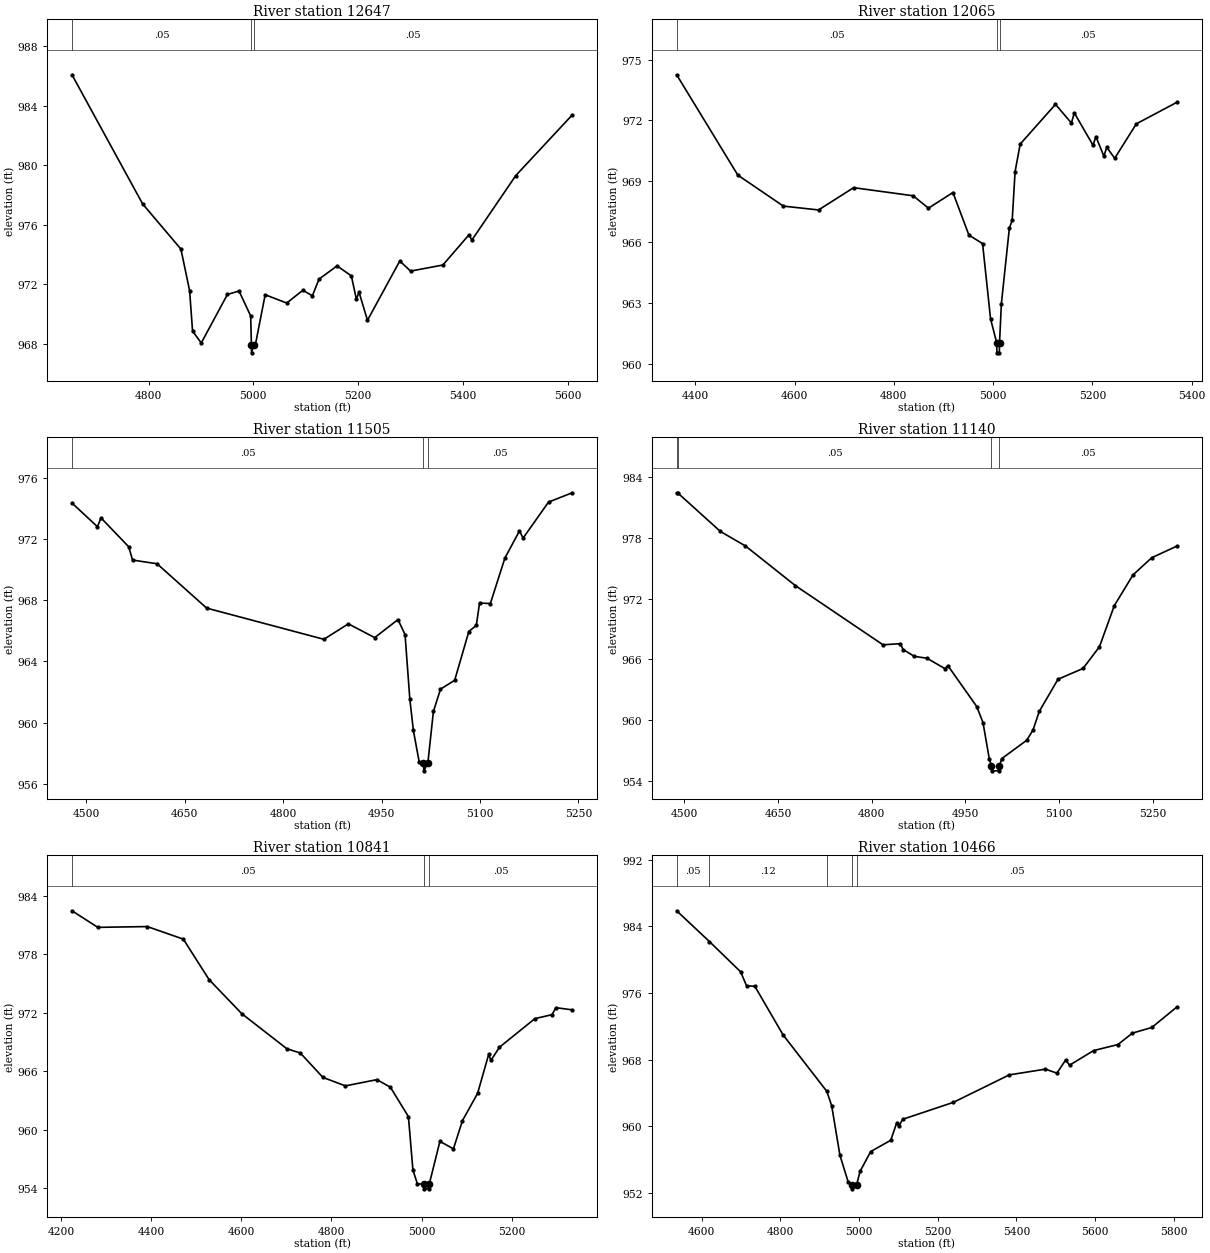
Type RM Length L Ch R = 1,12647,582,582,582
BEGIN DESCRIPTION:
LITTLE LLANO 065 25.0
END DESCRIPTION:
XS GIS Cut Line= 3
      2848855.66     10237053.12      2849163.75     10236895.00
      2849755.68     10236753.11
#Sta/Elev= 30
  4653.7  986.09  4788.6  977.40  4861.7  974.36  4878.3  971.56  4883.9  968.85
  4900.5  968.04  4950.5  971.31  4972.7  971.54  4994.9  969.86  4996.3  967.88
  4996.5  967.38  5000.3  967.88  5003.6  967.88  5022.6  971.29  5063.7  970.73
  5094.5  971.59  5112.7  971.22  5125.4  972.34  5159.8  973.23  5187.1  972.56
  5196.7  970.99  5201.8  971.46  5217.9  969.57  5279.6  973.56  5300.2  972.88
  5361.9  973.29  5411.9  975.33  5417.1  974.96  5501.1  979.31  5608.7  983.38
#Mann=3,-1,0
  4653.7    0.05       0  4996.3    0.03       0  5000.3    0.05       0
Bank Sta=4996.3,5000.3
Exp/Cntr=0.3,0.1

Type RM Length L Ch R = 1,12065,560,560,560
BEGIN DESCRIPTION:
LITTLE LLANO 065 24.0
END DESCRIPTION:
XS GIS Cut Line= 3
      2848902.70     10237744.24      2849228.24     10237408.28
      2849701.24     10237148.39
#Sta/Elev= 30
  4362.5  974.25  4485.7  969.30  4577.5  967.77  4648.3  967.58  4719.0  968.68
  4838.8  968.28  4869.8  967.67  4919.0  968.44  4951.2  966.34  4978.7  965.92
  4994.8  962.21  5007.1  961.03  5007.6  960.53  5012.4  960.53  5012.9  961.03
  5016.6  962.96  5032.7  966.68  5038.4  967.07  5044.2  969.47  5054.5  970.83
  5125.6  972.79  5157.7  971.87  5163.5  972.37  5201.3  970.77  5207.0  971.20
  5223.1  970.23  5228.8  970.67  5244.9  970.13  5288.5  971.83  5370.0  972.89
#Mann=3,-1,0
  4362.5    0.05       0  5007.1    0.03       0  5012.9    0.05       0
Bank Sta=5007.1,5012.9
Exp/Cntr=0.3,0.1

Type RM Length L Ch R = 1,11505,365,365,365
BEGIN DESCRIPTION:
LITTLE LLANO 065 23.0
END DESCRIPTION:
XS GIS Cut Line= 3
      2849005.69     10238053.11      2849571.99     10237822.34
      2849705.71     10237753.10
#Sta/Elev= 30
  4478.3  974.35  4517.1  972.80  4522.5  973.38  4564.7  971.49  4570.6  970.62
  4607.9  970.38  4683.5  967.48  4862.1  965.44  4899.4  966.45  4939.6  965.55
  4975.0  966.73  4985.8  965.75  4993.1  961.51  4998.5  959.48  5007.4  957.40
  5013.9  957.34  5014.4  956.84  5020.5  957.34  5029.0  960.72  5039.8  962.18
  5061.4  962.76  5083.0  965.95  5094.4  966.35  5099.3  967.81  5115.8  967.78
  5138.0  970.76  5160.1  972.52  5165.7  972.06  5204.4  974.41  5240.4  975.02
#Mann=3,-1,0
  4478.3    0.05       0  5013.9    0.03       0  5020.5    0.05       0
Bank Sta=5013.9,5020.5
Exp/Cntr=0.3,0.1

Type RM Length L Ch R = 1,11140,299,299,299
BEGIN DESCRIPTION:
LITTLE LLANO 065 22.0
END DESCRIPTION:
XS GIS Cut Line= 3
      2849705.68     10238653.12      2849689.18     10238257.24
      2849705.68     10237853.10
#Sta/Elev= 30
  4487.8  982.48  4489.3  982.48  4557.9  978.65  4597.9  977.22  4678.0  973.29
  4818.1  967.44  4845.5  967.55  4850.5  966.97  4868.1  966.30  4888.6  966.11
  4917.0  965.09  4922.0  965.38  4968.2  961.33  4978.2  959.75  4988.2  956.19
  4991.8  955.47  4992.3  954.97  5004.1  954.97  5004.6  955.47  5008.3  956.18
  5048.3  958.00  5058.3  959.01  5068.3  960.85  5098.3  964.03  5138.4  965.10
  5164.7  967.25  5188.4  971.31  5218.4  974.36  5248.5  976.06  5288.5  977.20
#Mann=4,-1,0
  4487.8    0.12       0  4489.3    0.05       0  4991.8    0.03       0
  5004.6    0.05       0
Bank Sta=4991.8,5004.6
Exp/Cntr=0.3,0.1

Type RM Length L Ch R = 1,10841,375,375,375
BEGIN DESCRIPTION:
LITTLE LLANO 065 21.0
END DESCRIPTION:
XS GIS Cut Line= 3
      2850006.89     10238900.46      2849988.66     10237999.43
      2849926.14     10237798.86
#Sta/Elev= 30
  4223.4  982.45  4280.8  980.75  4390.8  980.83  4470.8  979.54  4528.0  975.39
  4600.8  971.89  4700.8  968.30  4730.8  967.86  4780.9  965.36  4830.9  964.49
  4900.9  965.13  4930.9  964.35  4970.9  961.34  4980.9  955.87  4990.9  954.43
  5004.5  954.43  5005.0  953.93  5016.8  953.93  5017.3  954.43  5040.9  958.80
  5070.9  958.03  5090.9  960.92  5124.6  963.72  5149.2  967.71  5154.4  967.11
  5173.1  968.45  5252.0  971.39  5289.7  971.79  5298.8  972.51  5334.7  972.29
#Mann=3,-1,0
  4223.4    0.05       0  5004.5    0.05       0  5017.3    0.05       0
Bank Sta=5004.5,5017.3
Exp/Cntr=0.3,0.1

Type RM Length L Ch R = 1,10466,553,553,553
BEGIN DESCRIPTION:
LITTLE LLANO 065 20.0
END DESCRIPTION:
XS GIS Cut Line= 3
      2850611.08     10238463.00      2850165.74     10237793.70
      2850067.08     10237336.75
#Sta/Elev= 30
  4536.2  985.88  4619.5  982.19  4698.8  978.56  4713.8  976.89  4734.9  976.82
  4807.0  970.97  4917.9  964.22  4930.3  962.48  4951.3  956.54  4972.3  953.33
  4980.9  953.02  4981.4  952.52  4993.8  953.02  5002.4  954.61  5029.4  956.99
  5080.5  958.35  5095.6  960.44  5101.6  960.08  5110.6  960.86  5239.8  962.90
  5381.6  966.19  5473.7  966.88  5502.8  966.40  5524.9  967.97  5535.1  967.36
  5596.2  969.11  5657.9  969.83  5694.7  971.20  5744.0  971.88  5807.6  974.33
#Mann=5,-1,0
  4536.2    0.05       0  4619.5    0.12       0  4917.9    0.05       0
  4980.9    0.03       0  4993.8    0.05       0
Bank Sta=4980.9,4993.8
Exp/Cntr=0.3,0.1

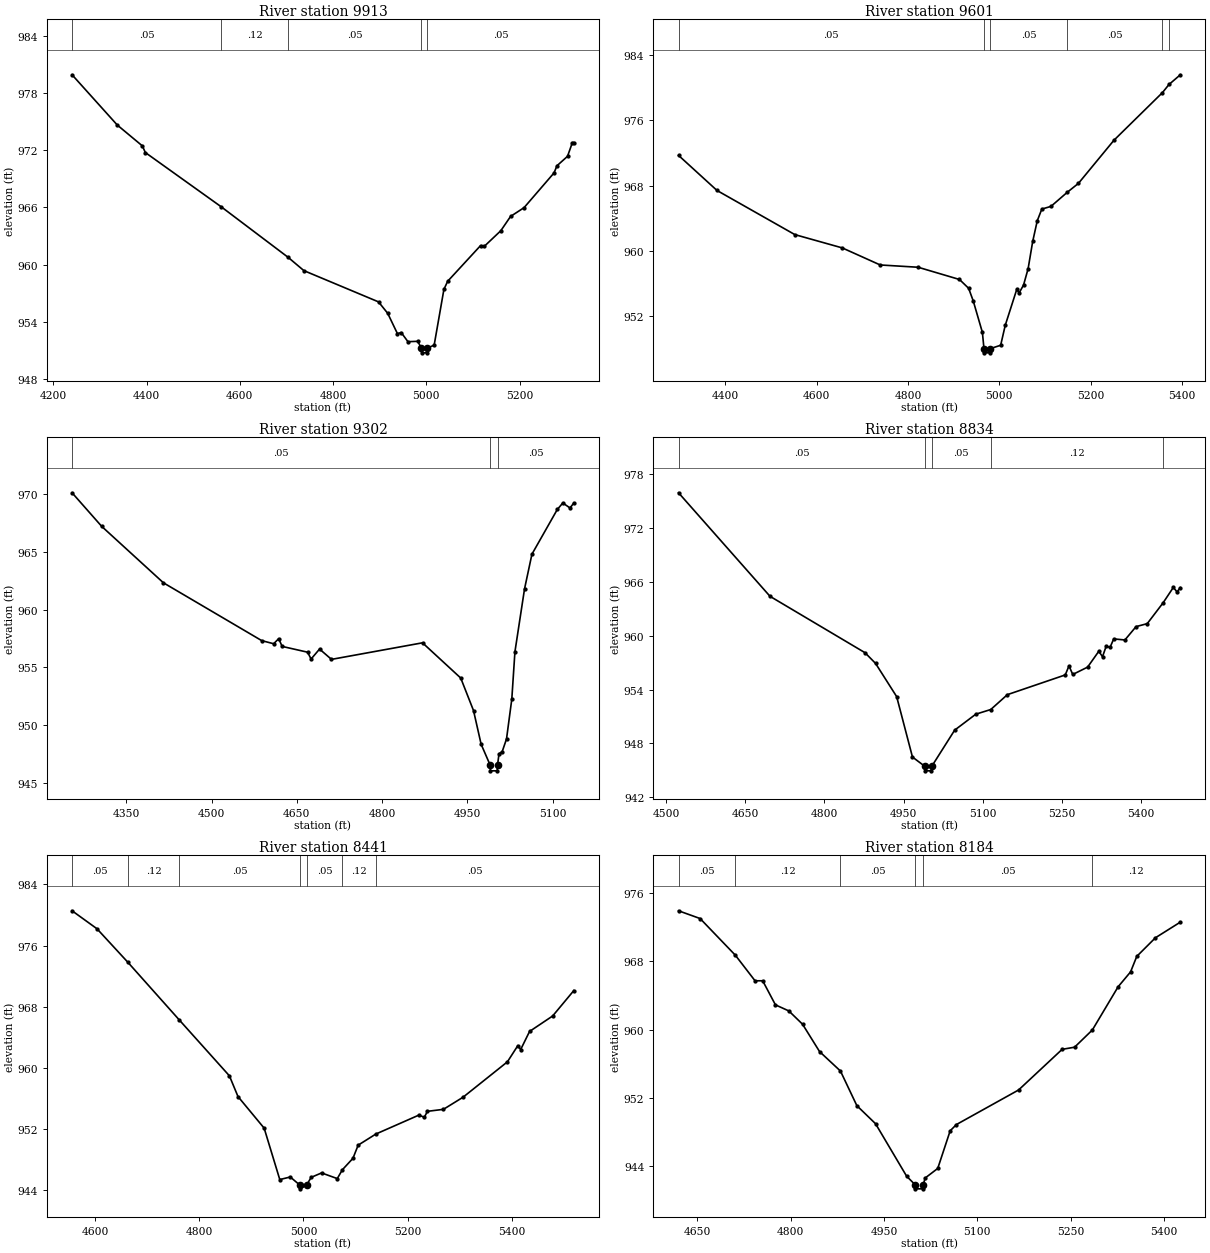
Type RM Length L Ch R = 1,9913,312,312,312
BEGIN DESCRIPTION:
LITTLE LLANO 065 19.0
END DESCRIPTION:
XS GIS Cut Line= 3
      2850759.49     10238390.09      2850764.70     10237736.40
      2850505.69     10237403.12
#Sta/Elev= 30
  4240.4  979.92  4337.4  974.64  4391.2  972.45  4397.4  971.76  4560.2  966.06
  4703.5  960.76  4737.4  959.36  4897.4  956.08  4917.1  954.88  4937.9  952.75
  4946.1  952.86  4960.5  951.90  4981.4  951.94  4989.3  951.23  4989.8  950.73
  5001.8  950.73  5002.3  951.23  5016.7  951.54  5037.6  957.39  5045.6  958.24
  5116.2  961.99  5124.4  961.92  5159.6  963.55  5180.5  965.05  5209.4  965.97
  5273.7  969.62  5280.0  970.37  5302.6  971.36  5313.0  972.80  5316.2  972.80
#Mann=5,-1,0
  4240.4    0.05       0  4560.2    0.12       0  4703.5    0.05       0
  4989.3    0.05       0  5002.3    0.05       0
Bank Sta=4989.3,5002.3
Exp/Cntr=0.3,0.1

Type RM Length L Ch R = 1,9601,299,299,299
BEGIN DESCRIPTION:
Mapping XS e433d680
END DESCRIPTION:
XS GIS Cut Line= 3
      2850848.03     10238288.52      2850991.26     10237770.26
      2851017.31     10237210.35
#Sta/Elev= 30
  4298.0  971.71  4382.2  967.41  4552.6  962.00  4656.4  960.37  4739.4  958.28
  4822.4  958.00  4912.9  956.50  4932.9  955.42  4943.0  953.87  4963.0  950.02
  4966.5  948.01  4967.0  947.51  4979.0  947.51  4979.5  948.01  5003.0  948.44
  5013.0  950.88  5038.3  955.30  5043.3  954.84  5053.1  955.82  5063.1  957.83
  5073.1  961.16  5083.1  963.70  5093.1  965.13  5113.1  965.46  5148.8  967.19
  5173.2  968.28  5251.0  973.57  5357.0  979.40  5371.4  980.40  5396.2  981.59
#Mann=6,-1,0
  4298.0    0.05       0  4966.5    0.07       0  4979.5    0.05       0
  5148.8    0.05       0  5357.0    0.12       0  5371.4    0.05       0
Bank Sta=4966.5,4979.5
Exp/Cntr=0.3,0.1

Type RM Length L Ch R = 1,9302,468,468,468
BEGIN DESCRIPTION:
LITTLE LLANO 065 18.0
END DESCRIPTION:
XS GIS Cut Line= 3
      2850884.51     10238285.85      2851223.03     10237788.49
      2851347.47     10237537.03
#Sta/Elev= 30
  4254.8  970.08  4306.9  967.18  4415.4  962.31  4588.2  957.32  4609.2  957.05
  4618.1  957.49  4624.1  956.82  4668.9  956.32  4675.0  955.73  4689.9  956.59
  4710.9  955.70  4870.9  957.13  4938.1  954.09  4960.6  951.28  4974.0  948.37
  4989.8  946.58  4990.3  946.08  5002.3  946.08  5002.8  946.58  5005.4  947.55
  5011.0  947.74  5018.6  948.83  5027.9  952.27  5033.4  956.36  5050.3  961.79
  5063.3  964.78  5107.9  968.64  5117.6  969.20  5130.2  968.77  5137.0  969.20
#Mann=3,-1,0
  4254.8    0.05       0  4989.8    0.05       0  5002.8    0.05       0
Bank Sta=4989.8,5002.8
Exp/Cntr=0.3,0.1

Type RM Length L Ch R = 1,8834,393,393,393
BEGIN DESCRIPTION:
Mapping XS 1b281f7b
END DESCRIPTION:
XS GIS Cut Line= 3
      2851657.93     10238426.53      2851624.08     10237762.45
      2851419.53     10237560.49
#Sta/Elev= 30
  4523.0  975.95  4696.6  964.40  4876.9  958.11  4896.9  956.92  4937.0  953.21
  4967.0  946.47  4990.5  945.43  4991.0  944.93  5003.1  944.93  5003.6  945.43
  5047.1  949.47  5087.2  951.25  5115.6  951.77  5147.2  953.43  5257.0  955.63
  5264.1  956.64  5271.2  955.68  5299.4  956.50  5320.7  958.27  5327.7  957.66
  5334.8  958.85  5341.9  958.69  5349.0  959.65  5370.2  959.53  5391.4  961.02
  5412.6  961.35  5442.9  963.69  5462.1  965.39  5469.2  964.89  5475.4  965.37
#Mann=5,-1,0
  4523.0    0.05       0  4990.5    0.05       0  5003.6    0.05       0
  5115.6    0.12       0  5442.9    0.05       0
Bank Sta=4990.5,5003.6
Exp/Cntr=0.3,0.1

Type RM Length L Ch R = 1,8441,257,257,257
BEGIN DESCRIPTION:
LITTLE LLANO 065 17.0
END DESCRIPTION:
XS GIS Cut Line= 3
      2852293.34     10237679.11      2851736.06     10237640.05
      2851355.70     10237503.12
#Sta/Elev= 30
  4556.1  980.55  4603.9  978.20  4662.9  973.84  4761.6  966.30  4858.0  958.98
  4874.5  956.27  4924.7  952.14  4954.7  945.42  4974.8  945.76  4993.0  944.71
  4993.5  944.21  5006.2  944.71  5014.9  945.71  5034.9  946.29  5065.0  945.55
  5074.9  946.71  5095.1  948.20  5105.1  949.92  5139.0  951.37  5221.4  953.84
  5232.1  953.57  5238.0  954.34  5268.7  954.60  5306.5  956.19  5391.5  960.81
  5411.6  962.94  5416.9  962.41  5434.0  964.78  5478.3  966.80  5519.0  970.13
#Mann=7,-1,0
  4556.1    0.05       0  4662.9    0.12       0  4761.6    0.05       0
  4993.0    0.05       0  5006.2    0.05       0  5074.9    0.12       0
  5139.0    0.05       0
Bank Sta=4993,5006.2
Exp/Cntr=0.3,0.1

Type RM Length L Ch R = 1,8184,230,230,230
BEGIN DESCRIPTION:
LITTLE LLANO 065 16.0
END DESCRIPTION:
XS GIS Cut Line= 3
      2852157.93     10237444.74      2851965.22     10237403.07
      2851355.69     10237403.11
#Sta/Elev= 30
  4619.6  973.91  4654.3  973.00  4711.0  968.70  4742.6  965.71  4754.9  965.71
  4775.4  962.89  4796.9  962.18  4819.0  960.62  4846.3  957.42  4879.9  955.14
  4906.3  951.08  4936.3  948.97  4986.3  942.82  4999.7  941.84  5000.2  941.34
  5012.4  941.34  5012.9  941.84  5016.3  942.62  5036.3  943.73  5056.3  948.14
  5066.3  948.87  5166.3  952.92  5236.3  957.68  5256.3  957.93  5284.9  959.95
  5326.3  965.01  5346.3  966.75  5356.3  968.57  5386.3  970.75  5426.3  972.58
#Mann=6,-1,0
  4619.6    0.05       0  4711.0    0.12       0  4879.9    0.05       0
  4999.7    0.05       0  5012.9    0.05       0  5284.9    0.12       0
Bank Sta=4999.7,5012.9
Exp/Cntr=0.3,0.1

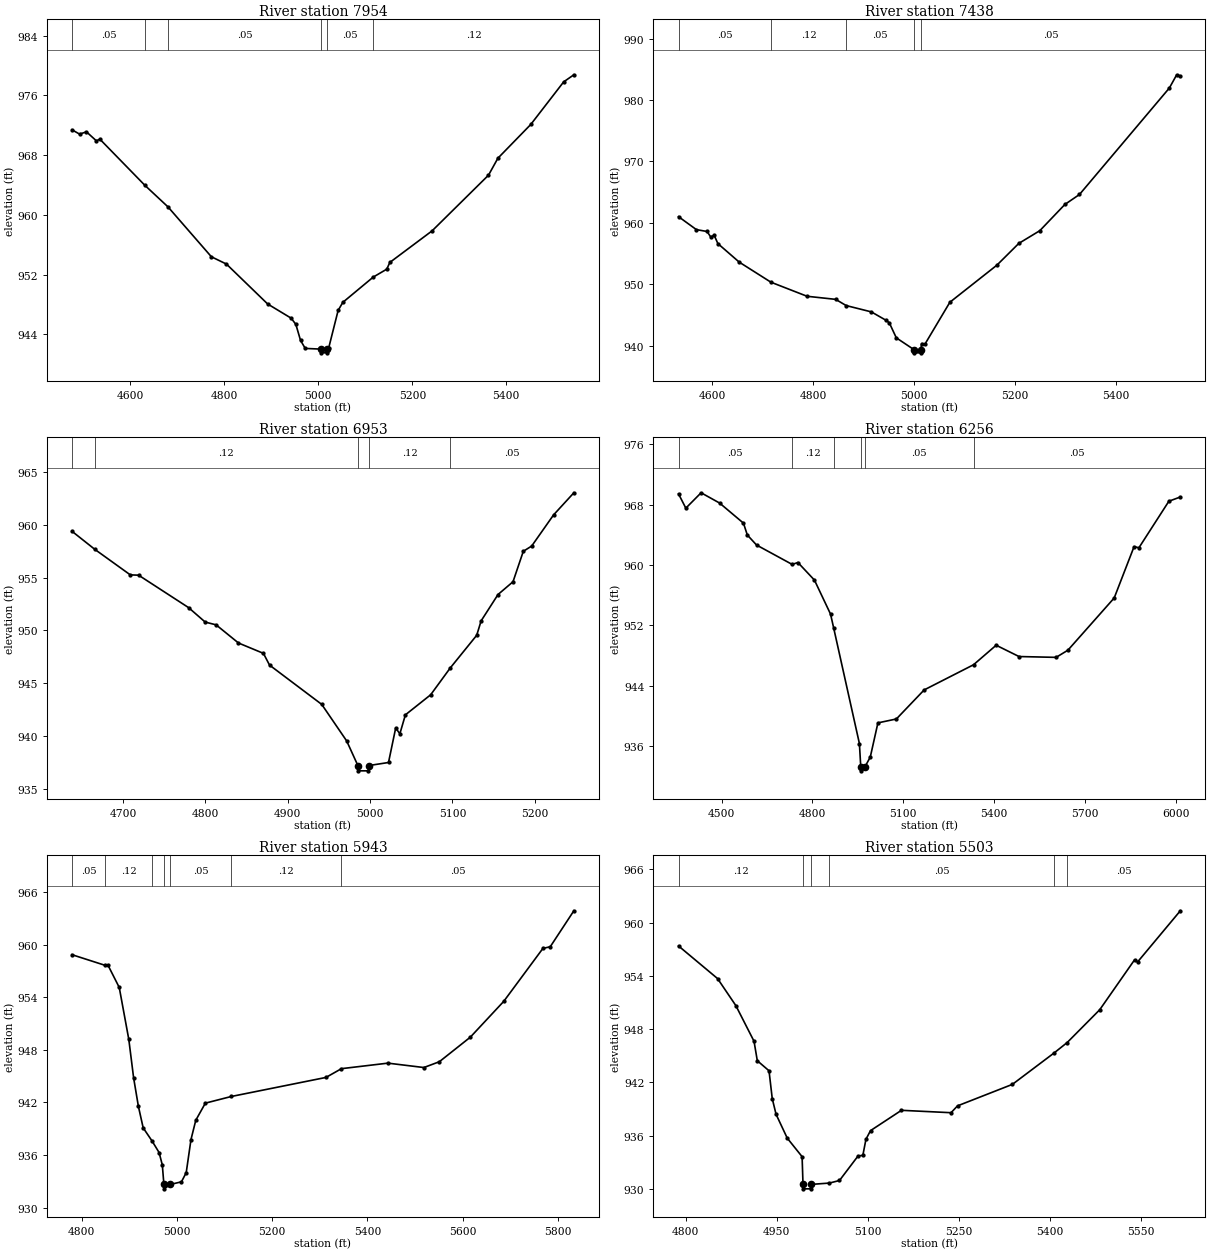
Type RM Length L Ch R = 1,7954,516,516,516
BEGIN DESCRIPTION:
LITTLE LLANO 065 15.0
END DESCRIPTION:
XS GIS Cut Line= 3
      2852194.42     10237366.63      2851926.16     10237181.72
      2851184.02     10237173.90
#Sta/Elev= 30
  4475.8  971.39  4491.7  970.82  4506.5  971.12  4527.5  969.92  4535.0  970.14
  4630.5  963.98  4679.9  961.08  4772.3  954.40  4804.4  953.42  4892.1  948.08
  4942.1  946.18  4952.1  945.35  4962.1  943.20  4972.1  942.13  5005.5  942.04
  5006.0  941.54  5018.2  941.54  5018.7  942.04  5022.1  942.22  5042.1  947.22
  5052.1  948.30  5116.8  951.68  5145.6  952.74  5152.1  953.64  5242.1  957.87
  5362.1  965.32  5382.1  967.59  5452.1  972.11  5522.1  977.81  5543.8  978.76
#Mann=6,-1,0
  4475.8    0.05       0  4630.5    0.12       0  4679.9    0.05       0
  5005.5    0.05       0  5018.7    0.05       0  5116.8    0.12       0
Bank Sta=5005.5,5018.7
Exp/Cntr=0.3,0.1

Type RM Length L Ch R = 1,7438,485,485,485
BEGIN DESCRIPTION:
LITTLE LLANO 065 14.0
END DESCRIPTION:
XS GIS Cut Line= 3
      2852105.71     10237003.14      2851770.50     10236679.00
      2851355.70     10236353.12
#Sta/Elev= 30
  4533.7  961.02  4569.1  958.91  4590.2  958.61  4597.4  957.72  4604.4  957.98
  4611.6  956.64  4654.0  953.62  4716.7  950.36  4788.3  948.07  4844.9  947.57
  4865.7  946.56  4915.6  945.53  4943.9  944.20  4951.1  943.76  4965.0  941.31
  5000.4  939.37  5000.9  938.87  5013.1  938.87  5013.6  939.37  5015.1  940.38
  5021.4  940.24  5071.1  947.10  5164.2  953.13  5207.6  956.67  5249.2  958.74
  5298.9  963.01  5327.8  964.63  5505.8  981.95  5520.3  984.10  5527.5  983.90
#Mann=5,-1,0
  4533.7    0.05       0  4716.7    0.12       0  4865.7    0.05       0
  5000.4    0.05       0  5013.6    0.05       0
Bank Sta=5000.4,5013.6
Exp/Cntr=0.3,0.1

Type RM Length L Ch R = 1,6953,697,697,697
BEGIN DESCRIPTION:
LITTLE LLANO 065 13.0
END DESCRIPTION:
XS GIS Cut Line= 3
      2852155.69     10236953.10      2852208.00     10236595.00
      2852155.68     10236353.09
#Sta/Elev= 30
  4638.1  959.37  4665.8  957.66  4708.8  955.25  4718.9  955.22  4779.6  952.15
  4799.8  950.78  4813.0  950.52  4840.2  948.80  4870.5  947.82  4877.9  946.71
  4941.3  942.99  4971.6  939.53  4985.2  937.20  4985.7  936.70  4998.0  936.70
  4998.5  937.20  5022.4  937.49  5031.1  940.75  5036.2  940.21  5042.9  942.00
  5073.6  943.90  5097.4  946.44  5129.5  949.53  5134.9  950.90  5155.4  953.39
  5173.6  954.60  5186.1  957.48  5196.3  957.98  5222.9  960.93  5247.5  963.02
#Mann=5,-1,0
  4638.1    0.05       0  4665.8    0.12       0  4985.2    0.07       0
  4998.5    0.12       0  5097.4    0.05       0
Bank Sta=4985.2,4998.5
Exp/Cntr=0.3,0.1

Type RM Length L Ch R = 1,6256,313,313,313
BEGIN DESCRIPTION:
LITTLE LLANO 065 12.0
END DESCRIPTION:
XS GIS Cut Line= 3
      2853087.62     10237374.43      2852795.95     10236577.55
      2852055.70     10236253.12
#Sta/Elev= 30
  4357.8  969.44  4381.9  967.55  4432.3  969.59  4493.3  968.23  4572.2  965.56
  4584.9  963.99  4615.4  962.66  4732.9  960.09  4752.0  960.34  4806.5  958.01
  4859.7  953.50  4869.9  951.68  4955.0  936.33  4959.5  933.21  4960.0  932.71
  4972.9  933.21  4990.9  934.54  5016.1  939.07  5077.1  939.59  5168.7  943.44
  5331.8  946.78  5406.5  949.37  5482.0  947.87  5604.4  947.76  5643.4  948.71
  5796.3  955.64  5861.8  962.44  5877.9  962.30  5976.8  968.47  6014.6  969.03
#Mann=6,-1,0
  4357.8    0.05       0  4732.9    0.12       0  4869.9    0.05       0
  4959.5    0.07       0  4972.9    0.05       0  5331.8    0.05       0
Bank Sta=4959.5,4972.9
Exp/Cntr=0.3,0.1

Type RM Length L Ch R = 1,5943,440,440,440
BEGIN DESCRIPTION:
Mapping XS ecfe1ab0
END DESCRIPTION:
XS GIS Cut Line= 3
      2853194.38     10236525.47      2852842.83     10236491.61
      2852173.58     10236283.29
#Sta/Elev= 30
  4779.7  958.84  4849.1  957.63  4855.1  957.65  4878.8  955.11  4898.9  949.18
  4909.0  944.80  4919.0  941.56  4929.1  939.10  4947.9  937.59  4962.5  936.29
  4969.3  934.87  4972.6  932.65  4973.1  932.15  4986.0  932.65  5009.5  932.95
  5019.5  934.00  5029.5  937.77  5039.6  939.97  5059.7  941.92  5114.3  942.68
  5313.0  944.85  5345.6  945.85  5443.2  946.48  5518.7  945.98  5551.2  946.64
  5616.3  949.44  5686.6  953.53  5768.8  959.56  5784.2  959.75  5833.8  963.85
#Mann=7,-1,0
  4779.7    0.05       0  4849.1    0.12       0  4947.9    0.05       0
  4972.6    0.05       0  4986.0    0.05       0  5114.3    0.12       0
  5345.6    0.05       0
Bank Sta=4972.6,4986
Exp/Cntr=0.3,0.1

Type RM Length L Ch R = 1,5503,490,490,490
BEGIN DESCRIPTION:
LITTLE LLANO 065 11.0
END DESCRIPTION:
XS GIS Cut Line= 3
      2853005.73     10236053.09      2852808.00     10236129.00
      2852205.65     10236253.12
#Sta/Elev= 30
  4788.2  957.36  4852.5  953.69  4882.6  950.65  4912.6  946.63  4918.0  944.44
  4937.3  943.31  4942.6  940.18  4948.9  938.41  4967.3  935.73  4991.8  933.64
  4993.3  930.52  4993.8  930.02  5006.2  930.02  5006.7  930.52  5036.8  930.67
  5053.4  930.96  5084.0  933.72  5091.9  933.79  5097.0  935.60  5104.5  936.57
  5155.5  938.86  5237.2  938.59  5247.9  939.36  5338.3  941.78  5407.1  945.32
  5428.6  946.49  5482.2  950.18  5539.5  955.79  5544.6  955.56  5615.0  961.32
#Mann=6,-1,0
  4788.2    0.12       0  4993.3    0.07       0  5006.7    0.12       0
  5036.8    0.05       0  5407.1    0.12       0  5428.6    0.05       0
Bank Sta=4993.3,5006.7
Exp/Cntr=0.3,0.1