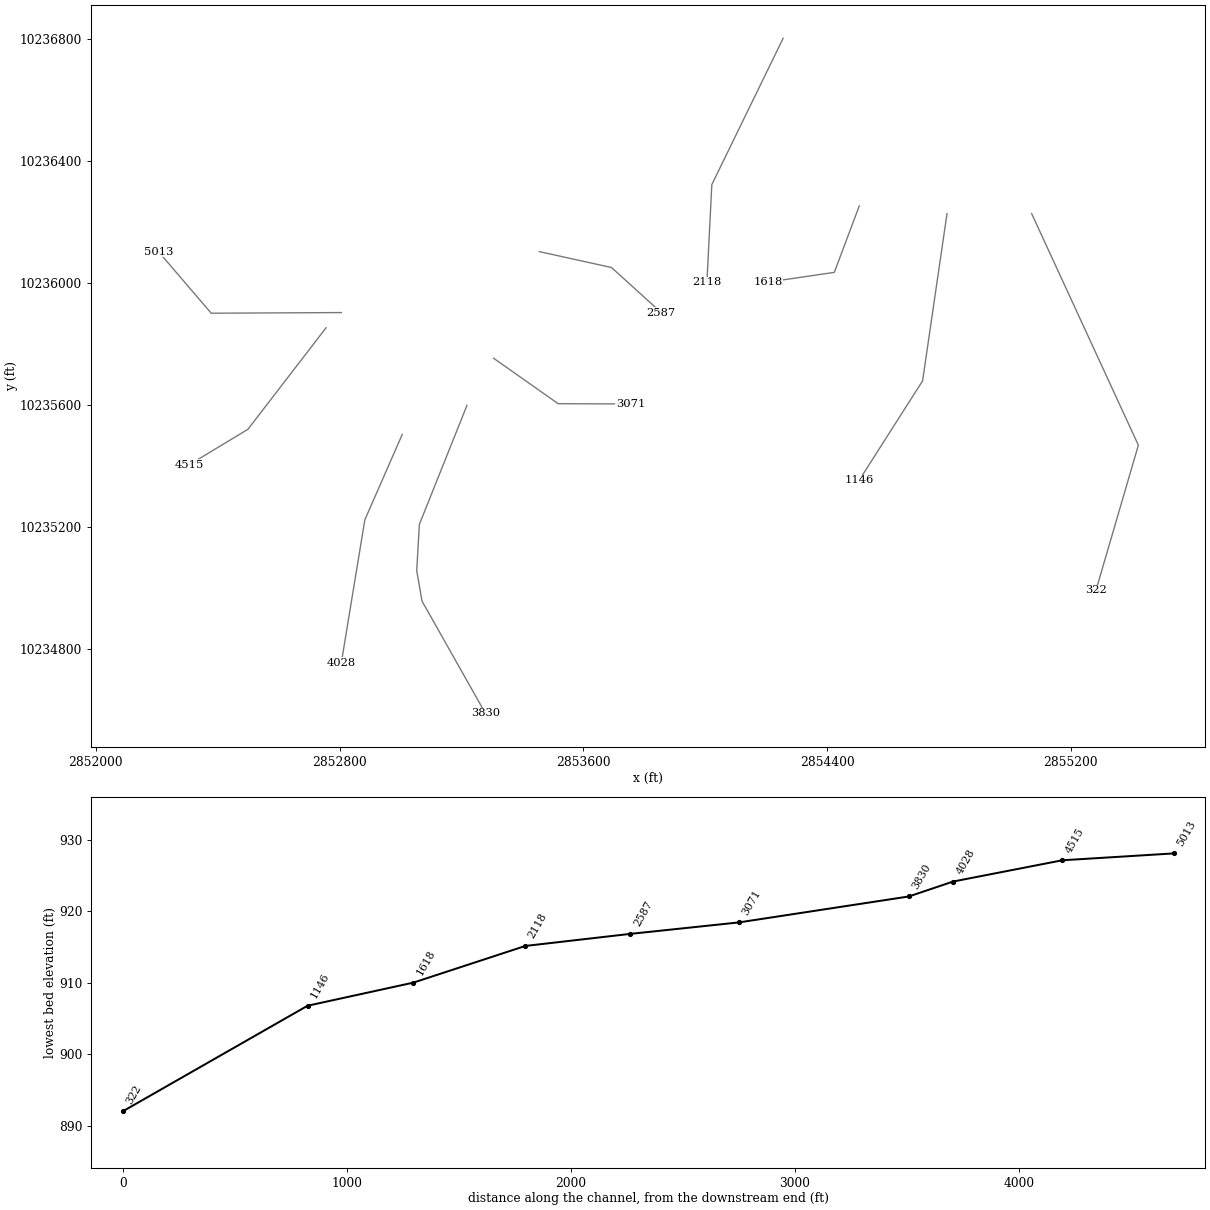
HEC-RAS study LITTLE LLANO 065.prj: LITTLE LLANO 065 Base Level Engineering

--- LITTLE LLANO 065.g01 (geometry) --- (continued)

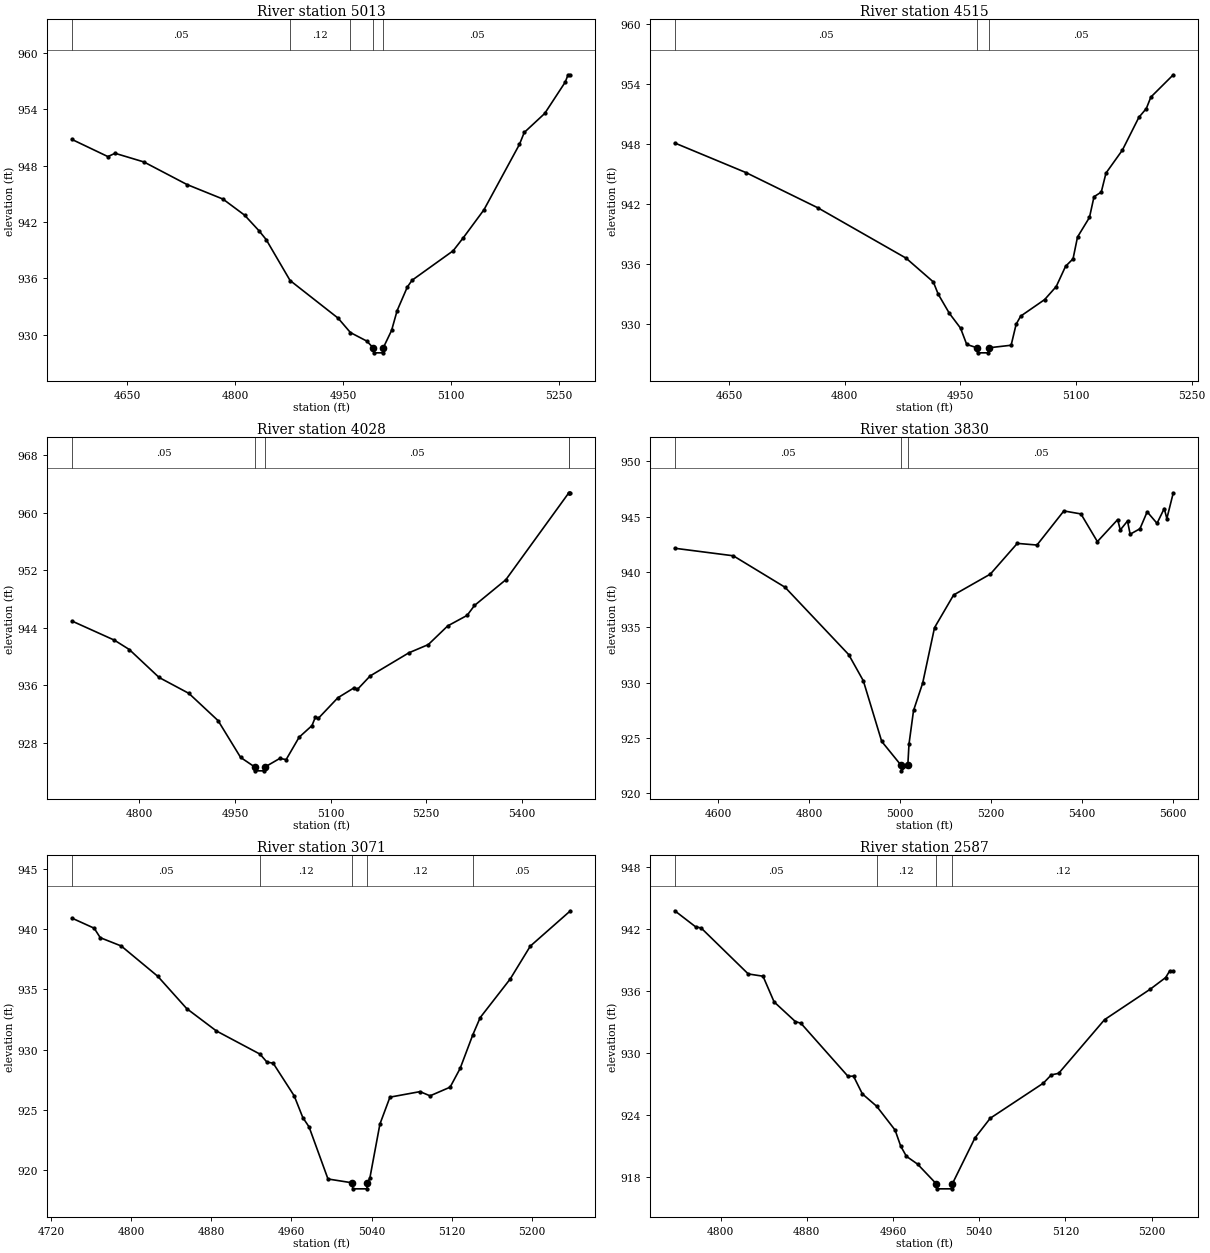
Type RM Length L Ch R = 1,5013,498,498,498
BEGIN DESCRIPTION:
LITTLE LLANO 065 10.0
END DESCRIPTION:
XS GIS Cut Line= 3
      2852805.64     10235903.11      2852378.75     10235901.00
      2852205.67     10236103.12
#Sta/Elev= 30
  4573.1  950.81  4623.1  948.98  4633.1  949.33  4673.1  948.41  4733.1  946.00
  4783.1  944.45  4813.1  942.74  4833.1  941.08  4843.1  940.14  4876.4  935.77
  4943.1  931.76  4960.3  930.22  4983.1  929.31  4992.3  928.56  4992.8  928.06
  5005.2  928.06  5005.7  928.56  5017.5  930.45  5025.2  932.56  5039.4  935.08
  5046.0  935.80  5103.1  938.94  5117.4  940.35  5145.9  943.31  5195.3  950.29
  5201.9  951.55  5230.4  953.58  5258.9  956.92  5262.8  957.70  5266.1  957.70
#Mann=5,-1,0
  4573.1    0.05       0  4876.4    0.12       0  4960.3    0.05       0
  4992.3    0.05       0  5005.7    0.05       0
Bank Sta=4992.3,5005.7
Exp/Cntr=0.3,0.1

Type RM Length L Ch R = 1,4515,487,487,487
BEGIN DESCRIPTION:
LITTLE LLANO 065 9.0
END DESCRIPTION:
XS GIS Cut Line= 3
      2852755.69     10235853.13      2852499.25     10235520.00
      2852305.70     10235403.12
#Sta/Elev= 30
  4579.6  948.08  4672.0  945.12  4765.4  941.59  4879.5  936.57  4914.9  934.19
  4921.2  932.97  4935.7  931.05  4950.2  929.57  4958.2  927.94  4971.8  927.60
  4972.3  927.10  4986.0  927.10  4986.5  927.60  5015.8  927.86  5022.3  929.96
  5028.2  930.77  5059.2  932.42  5074.3  933.73  5086.4  935.75  5096.1  936.50
  5101.9  938.68  5117.4  940.64  5123.3  942.71  5132.7  943.17  5138.8  945.07
  5160.1  947.37  5181.5  950.65  5191.1  951.52  5197.0  952.67  5226.1  954.90
#Mann=3,-1,0
  4579.6    0.05       0  4971.8    0.05       0  4986.5    0.05       0
Bank Sta=4971.8,4986.5
Exp/Cntr=0.3,0.1

Type RM Length L Ch R = 1,4028,198,198,198
BEGIN DESCRIPTION:
LITTLE LLANO 065 8.0
END DESCRIPTION:
XS GIS Cut Line= 3
      2853005.68     10235503.11      2852883.00     10235223.00
      2852805.69     10234753.12
#Sta/Elev= 30
  4694.2  944.96  4760.8  942.30  4784.2  941.00  4831.0  937.11  4877.7  934.90
  4923.5  931.11  4958.8  926.00  4981.6  924.63  4982.1  924.13  4995.9  924.13
  4996.4  924.63  5020.2  925.85  5030.3  925.70  5050.6  928.80  5070.8  930.42
  5075.9  931.55  5081.0  931.45  5111.4  934.29  5137.1  935.69  5142.1  935.45
  5162.0  937.32  5222.8  940.54  5253.2  941.68  5283.7  944.28  5314.1  945.74
  5325.7  947.12  5374.9  950.70  5473.4  962.75  5473.5  962.76  5476.2  962.79
#Mann=5,-1,0
  4694.2    0.05       0  4981.6    0.05       0  4996.4    0.05       0
  5473.4    0.12       0  5473.5    0.05       0
Bank Sta=4981.6,4996.4
Exp/Cntr=0.3,0.1

Type RM Length L Ch R = 1,3830,759,759,759
BEGIN DESCRIPTION:
Mapping XS d86a54c4
END DESCRIPTION:
XS GIS Cut Line= 5
      2853218.17     10235598.50      2853061.92     10235207.88
      2853053.24     10235055.97      2853070.60     10234956.14
      2853278.70     10234587.63
#Sta/Elev= 30
  4503.8  942.14  4632.6  941.46  4746.5  938.62  4886.6  932.54  4918.9  930.17
  4959.3  924.70  5002.0  922.54  5002.5  922.04  5016.8  922.54  5019.4  924.45
  5029.4  927.49  5049.5  929.96  5075.6  934.97  5117.6  937.92  5198.6  939.81
  5257.8  942.58  5301.1  942.43  5360.3  945.51  5397.9  945.24  5434.1  942.74
  5478.8  944.73  5484.5  943.79  5500.4  944.60  5506.2  943.41  5527.8  943.90
  5543.7  945.43  5565.4  944.39  5581.3  945.73  5587.0  944.82  5601.2  947.15
#Mann=3,-1,0
  4503.8    0.05       0  5002.0    0.05       0  5016.8    0.05       0
Bank Sta=5002,5016.8
Exp/Cntr=0.3,0.1

Type RM Length L Ch R = 1,3071,484,484,484
BEGIN DESCRIPTION:
LITTLE LLANO 065 6.0
END DESCRIPTION:
XS GIS Cut Line= 3
      2853305.71     10235753.09      2853517.50     10235604.00
      2853755.70     10235603.11
#Sta/Elev= 30
  4741.0  940.94  4763.2  940.10  4769.3  939.31  4790.2  938.62  4826.6  936.10
  4855.5  933.41  4885.1  931.55  4928.6  929.62  4935.6  928.95  4941.7  928.87
  4962.7  926.15  4971.3  924.34  4977.5  923.57  4996.4  919.23  5020.6  918.91
  5021.1  918.41  5035.2  918.41  5035.7  918.91  5038.2  919.32  5048.2  923.80
  5058.2  926.04  5088.2  926.50  5098.2  926.15  5118.2  926.87  5128.2  928.43
  5140.9  931.24  5148.2  932.66  5178.2  935.88  5198.2  938.61  5238.2  941.55
#Mann=5,-1,0
  4741.0    0.05       0  4928.6    0.12       0  5020.6    0.07       0
  5035.7    0.12       0  5140.9    0.05       0
Bank Sta=5020.6,5035.7
Exp/Cntr=0.3,0.1

Type RM Length L Ch R = 1,2587,469,469,469
BEGIN DESCRIPTION:
LITTLE LLANO 065 5.0
END DESCRIPTION:
XS GIS Cut Line= 3
      2853455.67     10236103.12      2853692.50     10236051.00
      2853855.66     10235903.13
#Sta/Elev= 30
  4757.5  943.75  4776.8  942.20  4782.0  942.08  4825.7  937.63  4839.4  937.41
  4849.7  934.92  4869.4  933.02  4874.6  932.85  4918.3  927.71  4923.4  927.73
  4931.6  926.01  4944.9  924.81  4962.0  922.50  4967.2  920.95  4972.5  919.96
  4982.8  919.21  5000.1  917.31  5000.6  916.81  5014.7  916.81  5015.2  917.31
  5036.1  921.74  5050.3  923.65  5099.6  927.05  5107.0  927.85  5113.8  928.00
  5156.4  933.20  5198.9  936.16  5213.1  937.28  5216.9  937.93  5220.2  937.93
#Mann=4,-1,0
  4757.5    0.05       0  4944.9    0.12       0  5000.1    0.07       0
  5015.2    0.12       0
Bank Sta=5000.1,5015.2
Exp/Cntr=0.3,0.1

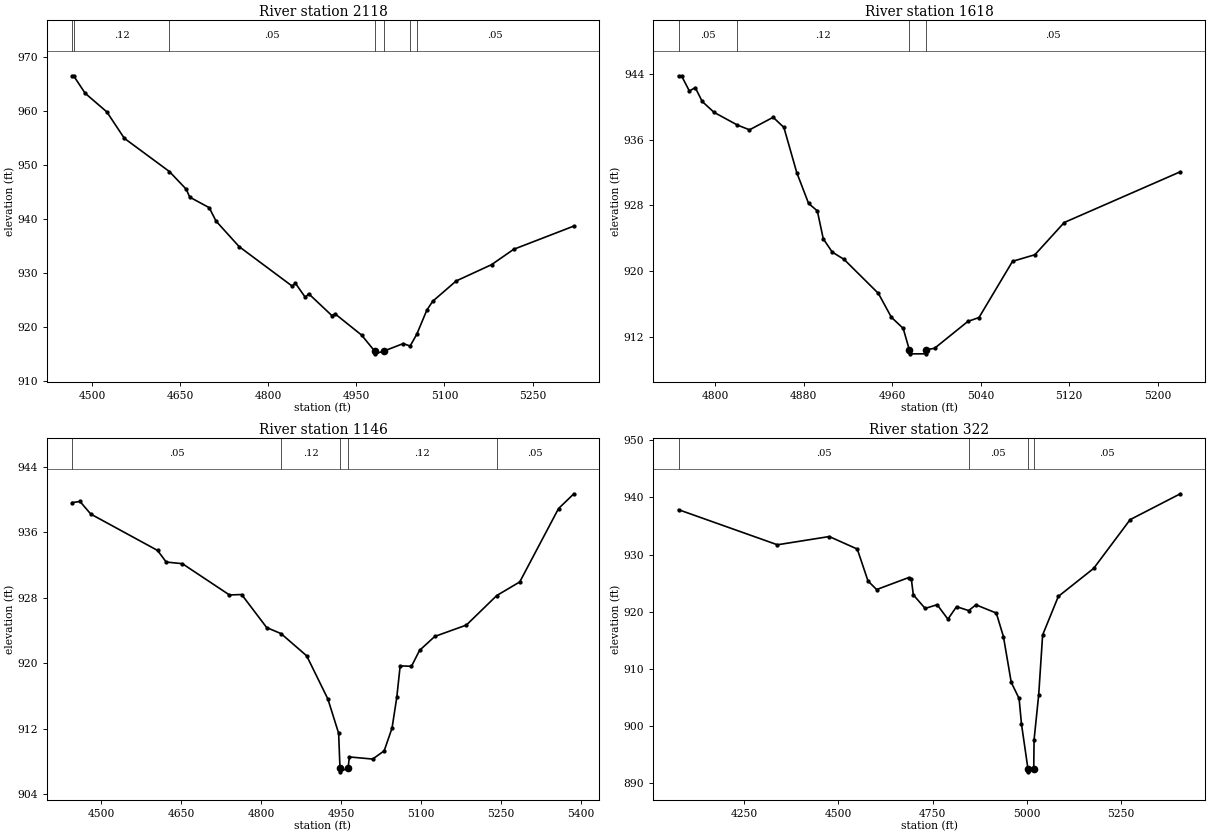
Type RM Length L Ch R = 1,2118,500,500,500
BEGIN DESCRIPTION:
LITTLE LLANO 065 4.0
END DESCRIPTION:
XS GIS Cut Line= 3
      2854255.70     10236803.14      2854021.75     10236323.00
      2854005.68     10236003.10
#Sta/Elev= 30
  4465.9  966.61  4468.5  966.61  4488.2  963.37  4525.1  959.92  4554.9  955.03
  4631.6  948.88  4660.3  945.60  4666.2  944.14  4699.5  942.18  4710.9  939.72
  4750.4  934.97  4840.6  927.67  4846.2  928.19  4863.1  925.57  4868.7  926.26
  4908.2  922.21  4913.8  922.52  4958.9  918.59  4981.2  915.62  4981.7  915.12
  4996.4  915.62  5029.9  917.02  5041.5  916.56  5052.8  918.74  5070.0  923.22
  5080.0  924.86  5120.0  928.62  5180.1  931.63  5217.9  934.48  5320.3  938.78
#Mann=7,-1,0
  4465.9    0.05       0  4468.5    0.12       0  4631.6    0.05       0
  4981.2    0.03       0  4996.4    0.05       0  5041.5    0.12       0
  5052.8    0.05       0
Bank Sta=4981.2,4996.4
Exp/Cntr=0.3,0.1

Type RM Length L Ch R = 1,1618,472,472,472
BEGIN DESCRIPTION:
LITTLE LLANO 065 3.0
END DESCRIPTION:
XS GIS Cut Line= 3
      2854505.69     10236253.12      2854423.75     10236035.00
      2854205.67     10236003.11
#Sta/Elev= 30
  4767.0  943.74  4769.7  943.74  4776.8  941.89  4782.1  942.31  4788.4  940.62
  4799.1  939.30  4820.2  937.76  4831.1  937.18  4852.5  938.70  4862.2  937.47
  4873.8  932.00  4884.5  928.25  4892.4  927.34  4897.8  923.94  4905.9  922.34
  4916.6  921.45  4947.6  917.32  4959.3  914.43  4970.0  913.08  4975.5  910.49
  4976.0  909.99  4990.2  909.99  4990.7  910.49  4998.3  910.66  5028.4  913.92
  5038.5  914.40  5068.8  921.22  5089.0  922.02  5115.5  925.93  5220.4  932.09
#Mann=4,-1,0
  4767.0    0.05       0  4820.2    0.12       0  4975.5    0.05       0
  4990.7    0.05       0
Bank Sta=4975.5,4990.7
Exp/Cntr=0.3,0.1

Type RM Length L Ch R = 1,1146,824,824,824
BEGIN DESCRIPTION:
LITTLE LLANO 065 2.0
END DESCRIPTION:
XS GIS Cut Line= 3
      2854793.70     10236227.87      2854713.50     10235679.00
      2854505.69     10235353.12
#Sta/Elev= 30
  4445.3  939.65  4460.2  939.79  4480.4  938.25  4605.6  933.81  4621.9  932.39
  4652.2  932.19  4740.5  928.37  4763.4  928.42  4810.4  924.38  4837.2  923.65
  4885.4  920.93  4925.1  915.66  4945.3  911.47  4947.8  907.26  4948.3  906.76
  4963.0  907.26  4965.5  908.58  5009.1  908.32  5030.7  909.32  5045.5  912.12
  5054.4  915.88  5060.7  919.71  5081.9  919.65  5097.1  921.60  5125.6  923.30
  5184.9  924.69  5241.9  928.30  5285.0  929.96  5357.7  938.92  5386.5  940.73
#Mann=5,-1,0
  4445.3    0.05       0  4837.2    0.12       0  4947.8    0.07       0
  4963.0    0.12       0  5241.9    0.05       0
Bank Sta=4947.8,4963
Exp/Cntr=0.3,0.1

Type RM Length L Ch R = 1,322,0,0,0
BEGIN DESCRIPTION:
LITTLE LLANO 065 1.0
END DESCRIPTION:
XS GIS Cut Line= 3
      2855071.47     10236227.85      2855421.67     10235467.79
      2855282.77     10234992.21
#Sta/Elev= 30
  4075.6  937.86  4338.1  931.72  4475.8  933.16  4550.2  930.97  4578.7  925.38
  4601.6  923.89  4686.4  925.98  4693.5  925.81  4699.0  922.96  4730.4  920.59
  4762.3  921.24  4790.8  918.71  4813.8  920.90  4846.0  920.21  4865.2  921.22
  4919.3  919.78  4938.2  915.67  4959.0  907.65  4979.8  904.84  4986.2  900.34
  5003.4  892.51  5003.9  892.01  5018.7  892.51  5019.6  897.62  5031.9  905.51
  5042.3  915.95  5084.0  922.69  5177.8  927.59  5274.7  936.12  5407.9  940.64
#Mann=4,-1,0
  4075.6    0.05       0  4846.0    0.05       0  5003.4    0.05       0
  5018.7    0.05       0
Bank Sta=5003.4,5018.7
Exp/Cntr=0.3,0.1

Chan Stop Cuts=-1