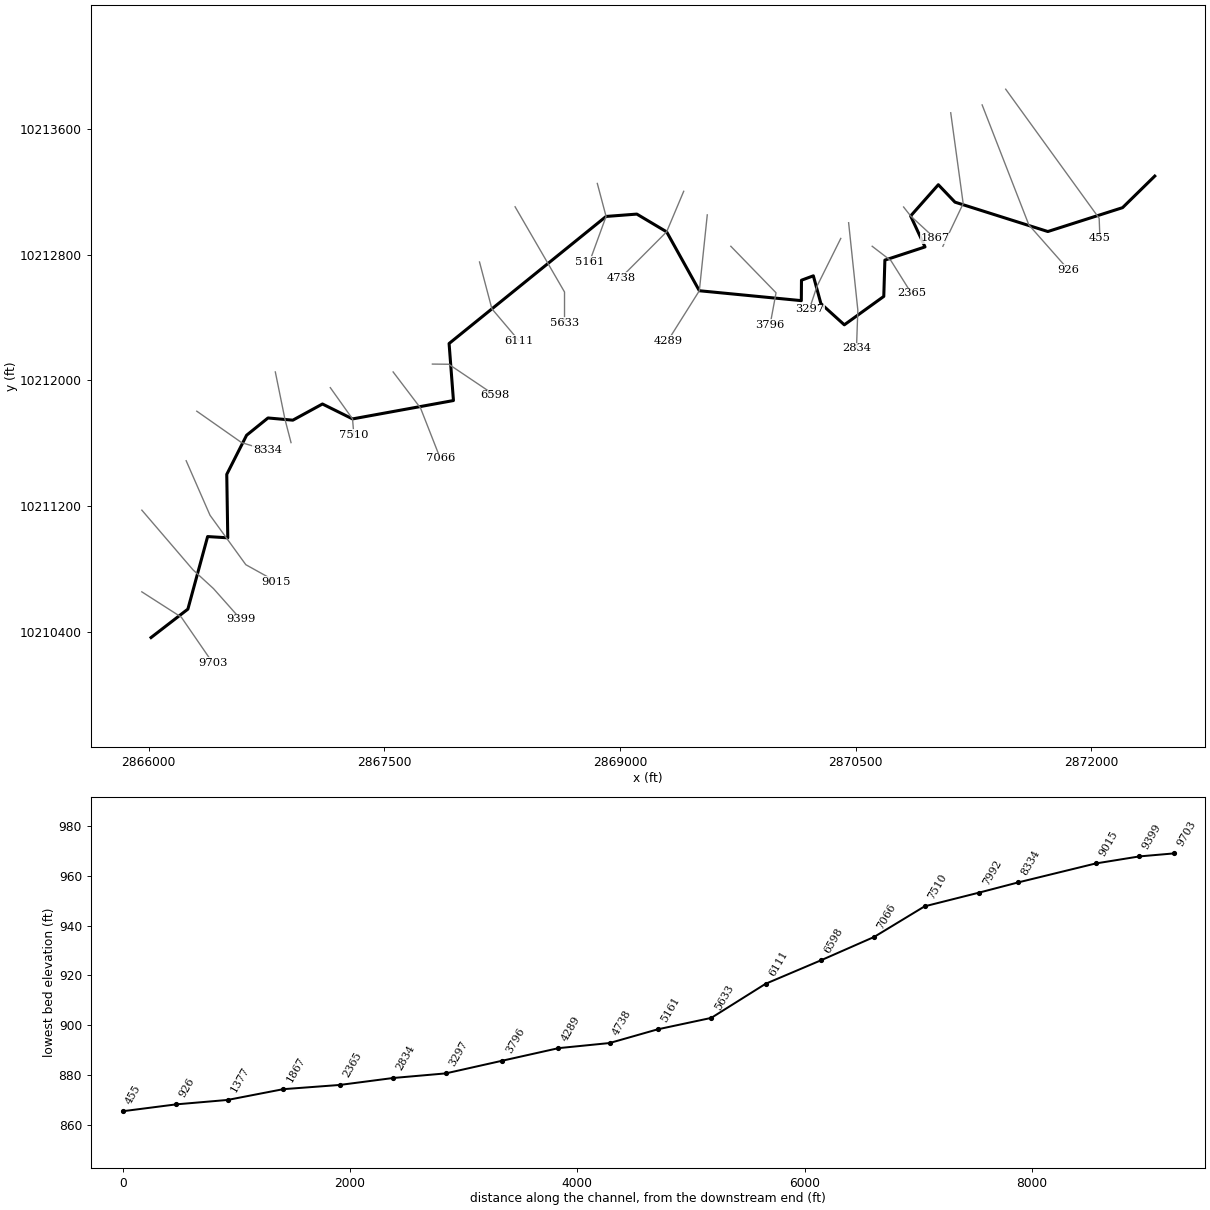
--- LITTLE LLANO 067.prj (project) ---

Proj Title=LITTLE LLANO 067 Base Level Engineering
Current Plan=p01
Default Exp/Contr=0.3,0.1
English Units
Geom File=g01
Flow File=f01
Plan File=p01
BEGIN DESCRIPTION:
LITTLE LLANO 067
END DESCRIPTION:

--- LITTLE LLANO 067.p01 (plan) ---

Plan Title=Multiple Run
Short Identifier=Multiple
Geom File=g01
Flow File=f01
Subcritical Flow
K Sum by GR= 0
Std Step Tol= 0.01
Critical Tol= 0.01
Num of Std Step Trials= 20
Max Error Tol= 0.3
Flow Tol Ratio= 0.001
Split Flow NTrial= 30
Split Flow Tol= 0.02
Split Flow Ratio= 0.02
Log Output Level= 0
Friction Slope Method= 1
Unsteady Friction Slope Method= 2
Unsteady Bridges Friction Slope Method= 1
Parabolic Critical Depth
Global Vel Dist=  1 , 1 , 1
Global Log Level= 0
CheckData=True
Encroach Param= -1, 0, 0, 0
BEGIN DESCRIPTION:
Multiple Run
END DESCRIPTION:

--- LITTLE LLANO 067.f01 (steady flow) ---

Flow Title=Multiple
Number of Profiles=7
Profile Names=10-year,25-year,50-year,1pct_min,100-year,1pct_plu,500-year
River Rch & RM= LITTLE LLANO 067,Reach-1,9703
     473     777    1106     784    1501    2875    2111
River Rch & RM= LITTLE LLANO 067,Reach-1,1377
     776    1309    2567    1916    3651    6956    5254
Boundary for River Rch & Prof#=LITTLE LLANO 067,Reach-1,1
Up Type=0
Dn Type=3
Dn Slope=0.005
Boundary for River Rch & Prof#=LITTLE LLANO 067,Reach-1,2
Up Type=0
Dn Type=3
Dn Slope=0.005
Boundary for River Rch & Prof#=LITTLE LLANO 067,Reach-1,3
Up Type=0
Dn Type=3
Dn Slope=0.005
Boundary for River Rch & Prof#=LITTLE LLANO 067,Reach-1,4
Up Type=0
Dn Type=3
Dn Slope=0.005
Boundary for River Rch & Prof#=LITTLE LLANO 067,Reach-1,5
Up Type=0
Dn Type=3
Dn Slope=0.005
Boundary for River Rch & Prof#=LITTLE LLANO 067,Reach-1,6
Up Type=0
Dn Type=3
Dn Slope=0.005
Boundary for River Rch & Prof#=LITTLE LLANO 067,Reach-1,7
Up Type=0
Dn Type=3
Dn Slope=0.005

--- LITTLE LLANO 067.g01 (geometry) ---

Geom Title=Existing Conditions

River Reach=LITTLE LLANO 067,Reach-1
Reach XY= 30
      2866014.50     10210362.00      2866249.00     10210543.00
      2866374.75     10211005.00      2866503.00     10210997.00
      2866496.50     10211401.00      2866622.75     10211650.00
      2866759.00     10211760.00      2866917.25     10211746.00
      2867105.75     10211849.00      2867297.25     10211754.00
      2867939.75     10211871.00      2867912.00     10212234.00
      2868911.50     10213043.00      2869107.25     10213058.00
      2869297.00     10212945.00      2869505.25     10212570.00
      2870154.50     10212507.00      2870155.50     10212637.00
      2870231.00     10212665.00      2870279.25     10212488.00
      2870428.25     10212353.00      2870679.50     10212534.00
      2870686.50     10212765.00      2870942.00     10212849.00
      2870850.50     10213046.00      2871026.75     10213245.00
      2871132.75     10213134.00      2871724.00     10212947.00
      2872199.75     10213099.00      2872404.75     10213300.00

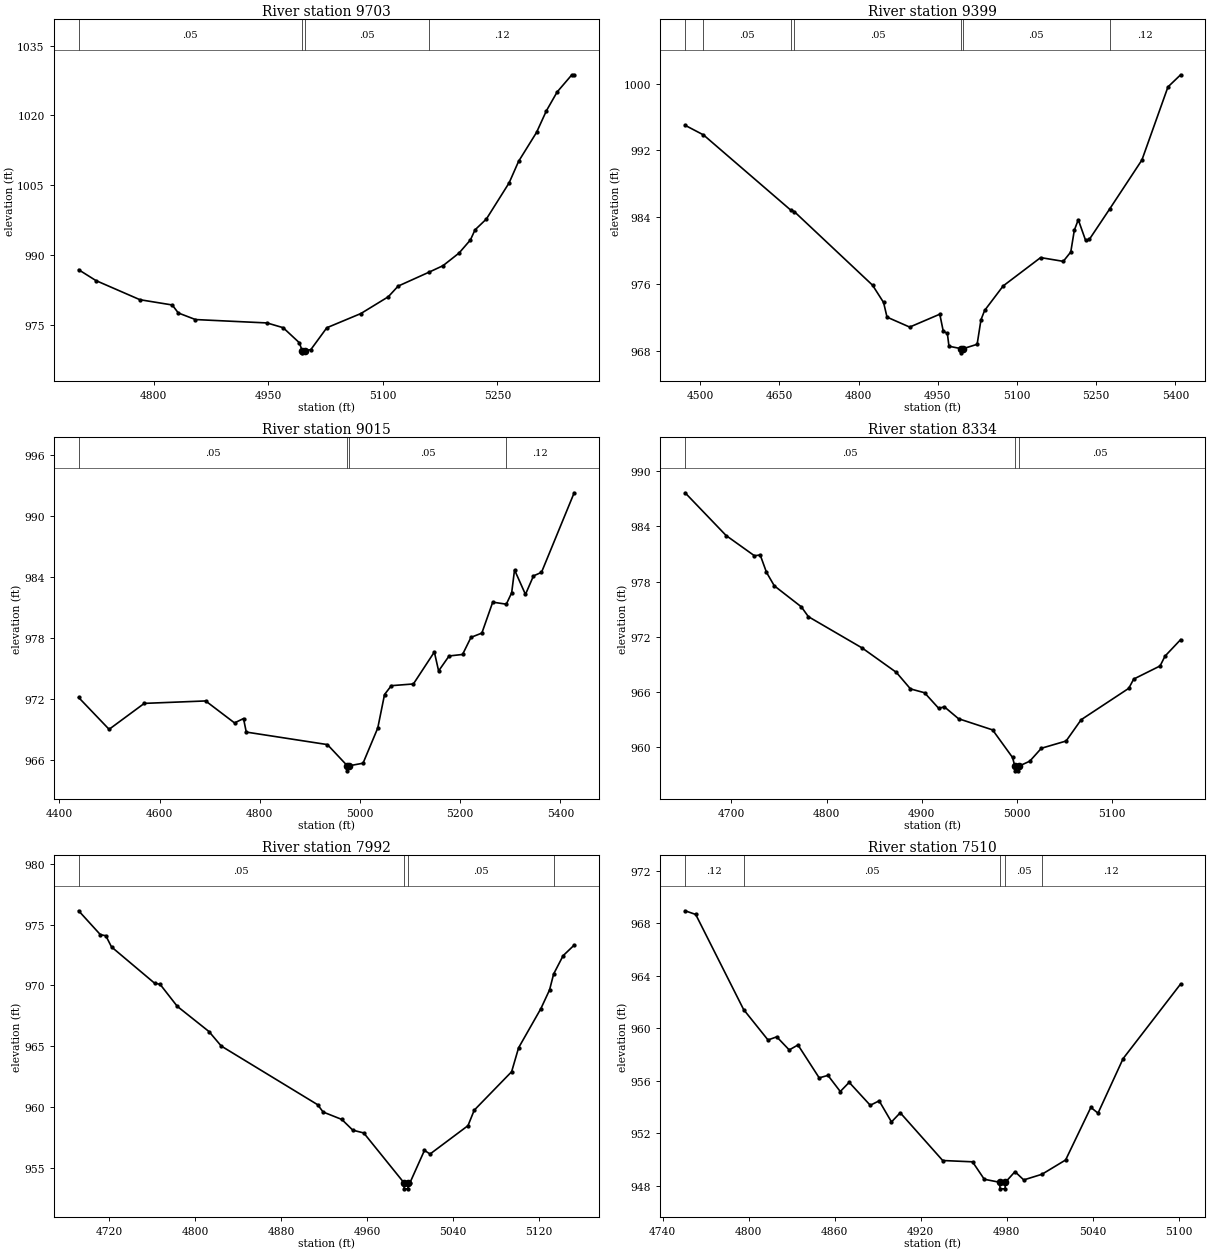
Type RM Length L Ch R = 1,9703,304,304,304
BEGIN DESCRIPTION:
LITTLE LLANO 067 21.0
END DESCRIPTION:
XS GIS Cut Line= 3
      2865955.70     10210653.10      2866207.00     10210492.00
      2866405.67     10210203.13
#Sta/Elev= 30
  4701.5  986.86  4724.3  984.52  4781.8  980.42  4824.1  979.29  4832.1  977.57
  4854.5  976.16  4948.3  975.43  4969.4  974.41  4990.6  971.18  4994.2  969.51
  4994.5  969.01  4998.2  969.51  5005.6  969.69  5026.6  974.40  5071.2  977.45
  5107.1  981.05  5120.0  983.34  5160.4  986.33  5178.8  987.73  5199.8  990.44
  5214.7  993.26  5220.7  995.42  5235.6  997.75  5265.4 1005.52  5277.8 1010.14
  5301.3 1016.35  5314.2 1020.99  5328.3 1025.04  5347.6 1028.73  5350.6 1028.73
#Mann=4,-1,0
  4701.5    0.05       0  4994.2    0.05       0  4998.2    0.05       0
  5160.4    0.12       0
Bank Sta=4994.2,4998.2
Exp/Cntr=0.3,0.1

Type RM Length L Ch R = 1,9399,384,384,384
BEGIN DESCRIPTION:
Mapping XS f9e66676
END DESCRIPTION:
XS GIS Cut Line= 4
      2865955.90     10211173.13      2866281.44     10210793.35
      2866411.65     10210673.99      2866585.28     10210478.65
#Sta/Elev= 30
  4471.7  995.01  4506.5  993.86  4671.3  984.89  4678.4  984.69  4826.6  975.89
  4847.5  973.82  4854.0  972.07  4896.9  970.88  4953.9  972.42  4960.5  970.38
  4968.2  970.13  4971.3  968.59  4994.2  968.30  4994.5  967.80  4998.2  968.30
  5024.6  968.82  5031.9  971.76  5038.8  972.87  5073.9  975.80  5144.8  979.19
  5187.7  978.74  5201.9  979.86  5208.6  982.46  5216.1  983.72  5230.0  981.24
  5237.0  981.36  5275.3  984.98  5336.6  990.86  5385.9  999.60  5409.9 1001.05
#Mann=7,-1,0
  4471.7    0.12       0  4506.5    0.05       0  4671.3    0.12       0
  4678.4    0.05       0  4994.2    0.05       0  4998.2    0.05       0
  5275.3    0.12       0
Bank Sta=4994.2,4998.2
Exp/Cntr=0.3,0.1

Type RM Length L Ch R = 1,9015,681,681,681
BEGIN DESCRIPTION:
Mapping XS 9bf55268
END DESCRIPTION:
XS GIS Cut Line= 4
      2866238.04     10211487.78      2866389.94     10211140.57
      2866617.81     10210825.90      2866811.27     10210718.42
#Sta/Elev= 30
  4438.5  972.18  4499.3  969.05  4569.5  971.60  4691.9  971.84  4749.6  969.68
  4767.5  970.11  4773.0  968.78  4934.9  967.55  4974.6  965.47  4974.9  964.97
  4978.6  965.47  5006.0  965.72  5035.4  969.18  5048.9  972.47  5062.4  973.34
  5106.5  973.51  5148.3  976.65  5156.8  974.79  5177.7  976.26  5204.6  976.41
  5221.4  978.09  5243.1  978.51  5264.8  981.55  5291.9  981.35  5302.6  982.47
  5308.3  984.72  5330.1  982.31  5346.1  984.13  5362.1  984.48  5427.3  992.30
#Mann=4,-1,0
  4438.5    0.05       0  4974.6    0.03       0  4978.6    0.05       0
  5291.9    0.12       0
Bank Sta=4974.6,4978.6
Exp/Cntr=0.3,0.1

Type RM Length L Ch R = 1,8334,342,342,342
BEGIN DESCRIPTION:
LITTLE LLANO 067 18.0
END DESCRIPTION:
XS GIS Cut Line= 3
      2866305.69     10211803.11      2866591.25     10211603.00
      2866755.65     10211553.12
#Sta/Elev= 30
  4651.3  987.67  4694.4  983.01  4724.1  980.81  4730.2  980.89  4736.8  979.00
  4745.0  977.53  4773.4  975.24  4780.8  974.17  4837.4  970.75  4873.2  968.10
  4888.0  966.30  4902.8  965.88  4917.6  964.19  4923.7  964.34  4938.5  963.05
  4974.3  961.83  4995.2  958.83  4997.7  957.87  4997.9  957.37  5001.4  957.37
  5001.7  957.87  5013.3  958.42  5025.5  959.83  5051.5  960.62  5067.3  962.94
  5117.3  966.36  5122.5  967.37  5150.2  968.80  5155.4  969.87  5171.8  971.67
#Mann=3,-1,0
  4651.3    0.05       0  4997.7    0.05       0  5001.7    0.05       0
Bank Sta=4997.7,5001.7
Exp/Cntr=0.3,0.1

Type RM Length L Ch R = 1,7992,482,482,482
BEGIN DESCRIPTION:
LITTLE LLANO 067 17.0
END DESCRIPTION:
XS GIS Cut Line= 3
      2866805.69     10212053.09      2866867.25     10211751.00
      2866905.68     10211603.11
#Sta/Elev= 30
  4691.7  976.13  4711.9  974.17  4717.0  974.08  4722.3  973.16  4762.4  970.18
  4767.5  970.09  4783.5  968.28  4813.0  966.21  4824.4  965.02  4914.1  960.20
  4919.2  959.60  4936.6  958.99  4946.8  958.11  4957.0  957.88  4994.4  953.79
  4994.6  953.29  4998.1  953.29  4998.4  953.79  5000.0  953.79  5013.5  956.45
  5018.7  956.15  5054.0  958.48  5059.8  959.75  5094.6  962.91  5101.1  964.88
  5121.8  968.09  5129.9  969.63  5133.7  970.94  5142.5  972.44  5152.8  973.31
#Mann=4,-1,0
  4691.7    0.05       0  4994.4    0.05       0  4998.4    0.05       0
  5133.7    0.12       0
Bank Sta=4994.4,4998.4
Exp/Cntr=0.3,0.1

Type RM Length L Ch R = 1,7510,444,444,444
BEGIN DESCRIPTION:
LITTLE LLANO 067 16.0
END DESCRIPTION:
XS GIS Cut Line= 3
      2867155.69     10211953.11      2867297.25     10211754.00
      2867305.68     10211653.15
#Sta/Elev= 30
  4755.7  968.95  4763.1  968.67  4796.5  961.42  4813.5  959.10  4819.6  959.34
  4828.3  958.34  4834.4  958.72  4849.2  956.21  4855.3  956.40  4863.9  955.17
  4870.1  955.87  4884.8  954.12  4891.0  954.46  4899.6  952.85  4905.7  953.55
  4935.3  949.91  4956.1  949.81  4964.3  948.48  4975.0  948.25  4975.3  947.75
  4978.8  947.75  4979.0  948.25  4985.7  949.06  4991.8  948.43  5004.5  948.86
  5021.0  949.95  5038.6  953.96  5043.6  953.52  5061.1  957.68  5101.2  963.37
#Mann=5,-1,0
  4755.7    0.12       0  4796.5    0.05       0  4975.0    0.05       0
  4979.0    0.05       0  5004.5    0.12       0
Bank Sta=4975,4979
Exp/Cntr=0.3,0.1

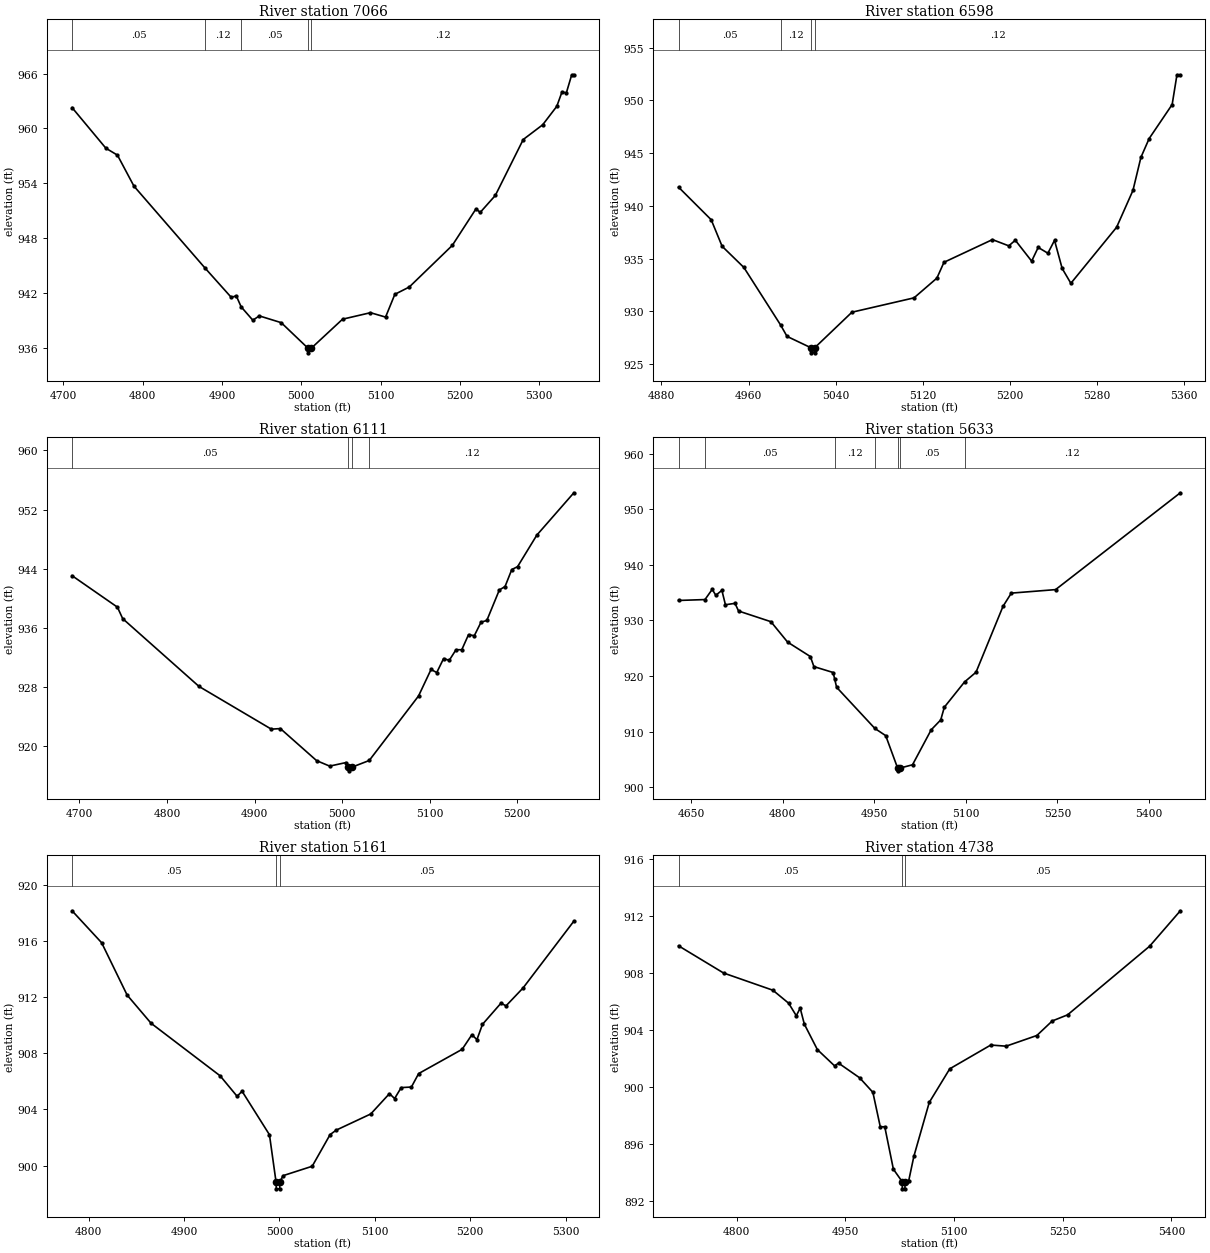
Type RM Length L Ch R = 1,7066,468,468,468
BEGIN DESCRIPTION:
LITTLE LLANO 067 15.0
END DESCRIPTION:
XS GIS Cut Line= 3
      2867555.70     10212053.09      2867730.25     10211823.00
      2867855.68     10211503.11
#Sta/Elev= 30
  4711.2  962.28  4753.8  957.84  4768.4  957.08  4789.2  953.69  4878.8  944.73
  4911.9  941.52  4918.1  941.70  4924.3  940.49  4939.0  939.03  4947.2  939.50
  4974.8  938.76  5008.6  935.96  5008.9  935.46  5012.6  935.96  5052.1  939.14
  5087.3  939.85  5106.3  939.37  5118.0  941.86  5136.2  942.66  5190.4  947.21
  5220.2  951.20  5225.6  950.82  5244.6  952.67  5279.8  958.79  5304.3  960.40
  5322.1  962.42  5328.7  964.01  5334.1  963.88  5340.9  965.87  5343.6  965.87
#Mann=5,-1,0
  4711.2    0.05       0  4878.8    0.12       0  4924.3    0.05       0
  5008.6    0.05       0  5012.6    0.12       0
Bank Sta=5008.6,5012.6
Exp/Cntr=0.3,0.1

Type RM Length L Ch R = 1,6598,487,487,487
BEGIN DESCRIPTION:
LITTLE LLANO 067 14.0
END DESCRIPTION:
XS GIS Cut Line= 3
      2867805.71     10212103.11      2867910.00     10212102.00
      2868205.73     10211903.08
#Sta/Elev= 30
  4895.7  941.77  4925.7  938.68  4935.7  936.17  4955.7  934.16  4989.4  928.71
  4995.3  927.63  5016.9  926.57  5017.1  926.07  5020.6  926.07  5020.9  926.57
  5054.9  929.92  5111.9  931.28  5132.9  933.15  5139.4  934.65  5183.9  936.80
  5198.9  936.21  5204.9  936.74  5219.9  934.76  5225.9  936.06  5234.8  935.51
  5240.9  936.73  5247.9  934.07  5255.9  932.66  5297.9  937.97  5312.9  941.46
  5320.2  944.59  5327.8  946.38  5348.9  949.60  5353.3  952.42  5356.4  952.42
#Mann=4,-1,0
  4895.7    0.05       0  4989.4    0.12       0  5016.9    0.07       0
  5020.9    0.12       0
Bank Sta=5016.9,5020.9
Exp/Cntr=0.3,0.1

Type RM Length L Ch R = 1,6111,478,478,478
BEGIN DESCRIPTION:
LITTLE LLANO 067 13.0
END DESCRIPTION:
XS GIS Cut Line= 3
      2868105.67     10212753.16      2868184.50     10212455.00
      2868355.69     10212253.11
#Sta/Elev= 30
  4691.6  943.05  4743.4  938.79  4749.4  937.24  4836.5  928.07  4919.2  922.28
  4929.5  922.36  4970.9  918.02  4985.8  917.28  5004.5  917.76  5007.3  917.14
  5007.5  916.64  5011.3  917.14  5031.0  918.04  5087.3  926.77  5101.6  930.36
  5108.1  929.94  5115.9  931.83  5122.4  931.60  5130.1  933.03  5136.7  933.03
  5144.4  935.07  5151.0  934.93  5158.7  936.76  5165.3  936.99  5179.6  941.12
  5186.1  941.58  5193.8  943.88  5200.4  944.27  5222.4  948.54  5264.7  954.27
#Mann=4,-1,0
  4691.6    0.05       0  5007.3    0.05       0  5011.3    0.05       0
  5031.0    0.12       0
Bank Sta=5007.3,5011.3
Exp/Cntr=0.3,0.1

Type RM Length L Ch R = 1,5633,472,472,472
BEGIN DESCRIPTION:
Mapping XS ea799b0e
END DESCRIPTION:
XS GIS Cut Line= 3
      2868332.20     10213104.57      2868646.89     10212562.01
      2868646.89     10212367.42
#Sta/Elev= 30
  4629.5  933.59  4672.8  933.75  4684.7  935.59  4690.5  934.52  4700.5  935.40
  4706.3  932.82  4722.0  933.07  4727.8  931.69  4780.8  929.77  4808.1  926.10
  4845.4  923.50  4851.2  921.69  4882.7  920.63  4885.3  919.42  4888.4  917.97
  4951.0  910.57  4968.8  909.27  4988.3  903.44  4988.5  902.94  4992.3  903.44
  5012.7  904.03  5043.3  910.32  5058.9  912.10  5064.8  914.39  5097.9  918.93
  5116.7  920.68  5160.9  932.53  5174.5  934.91  5247.0  935.54  5451.3  952.96
#Mann=7,-1,0
  4629.5    0.12       0  4672.8    0.05       0  4885.3    0.12       0
  4951.0    0.05       0  4988.3    0.05       0  4992.3    0.05       0
  5097.9    0.12       0
Bank Sta=4988.3,4992.3
Exp/Cntr=0.3,0.1

Type RM Length L Ch R = 1,5161,423,423,423
BEGIN DESCRIPTION:
LITTLE LLANO 067 11.0
END DESCRIPTION:
XS GIS Cut Line= 3
      2868855.68     10213253.11      2868911.50     10213043.00
      2868805.68     10212753.11
#Sta/Elev= 30
  4782.6  918.17  4813.6  915.89  4840.3  912.16  4865.4  910.15  4937.8  906.40
  4955.6  904.94  4960.8  905.30  4989.5  902.20  4996.4  898.84  4996.7  898.34
  5000.2  898.34  5000.4  898.84  5003.8  899.28  5034.3  899.95  5053.1  902.21
  5059.6  902.53  5095.7  903.68  5115.3  905.13  5120.7  904.78  5127.6  905.56
  5138.3  905.60  5145.9  906.56  5191.5  908.29  5201.7  909.33  5207.0  908.98
  5212.8  910.07  5232.2  911.58  5237.5  911.39  5255.4  912.67  5308.6  917.43
#Mann=3,-1,0
  4782.6    0.05       0  4996.4    0.05       0  5000.4    0.05       0
Bank Sta=4996.4,5000.4
Exp/Cntr=0.3,0.1

Type RM Length L Ch R = 1,4738,449,449,449
BEGIN DESCRIPTION:
LITTLE LLANO 067 10.0
END DESCRIPTION:
XS GIS Cut Line= 3
      2869405.70     10213203.15      2869297.00     10212945.00
      2869005.68     10212653.10
#Sta/Elev= 30
  4719.9  909.91  4782.0  908.00  4850.1  906.79  4871.8  905.88  4882.4  905.00
  4887.8  905.53  4893.5  904.41  4911.5  902.62  4935.2  901.48  4940.7  901.67
  4969.8  900.64  4988.1  899.62  4998.3  897.20  5004.5  897.20  5016.4  894.22
  5028.6  893.34  5028.8  892.84  5032.3  892.84  5032.6  893.34  5037.6  893.42
  5044.7  895.13  5065.9  898.91  5094.2  901.27  5150.8  902.94  5172.0  902.86
  5214.4  903.61  5235.6  904.63  5256.8  905.06  5370.0  909.88  5412.4  912.37
#Mann=3,-1,0
  4719.9    0.05       0  5028.6    0.05       0  5032.6    0.05       0
Bank Sta=5028.6,5032.6
Exp/Cntr=0.3,0.1

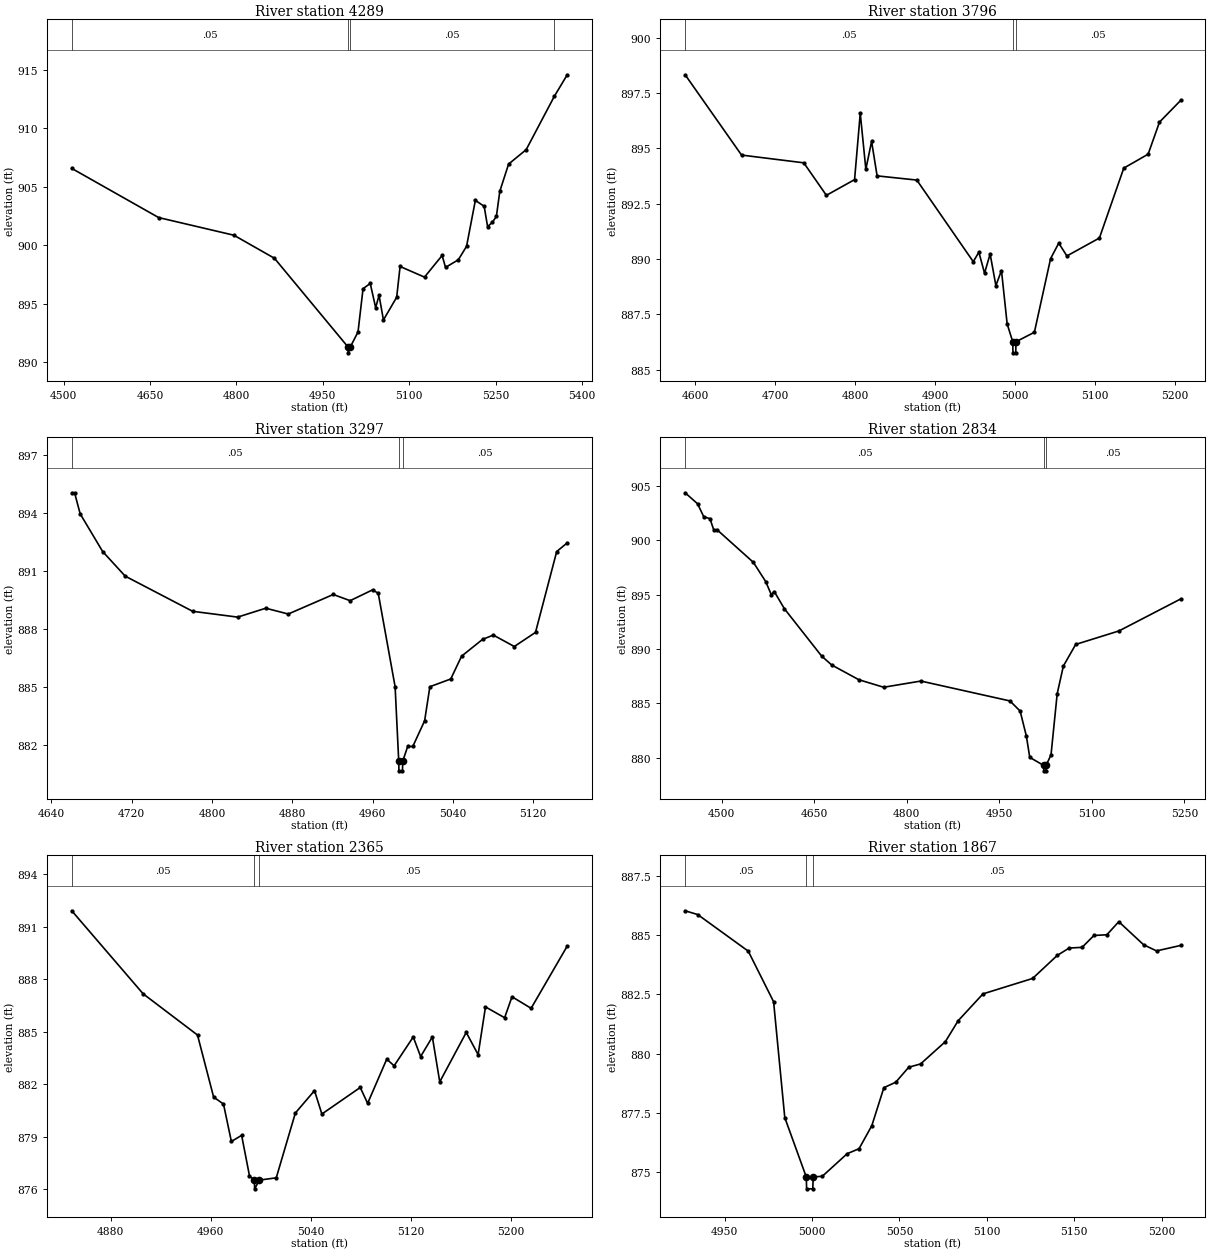
Type RM Length L Ch R = 1,4289,493,493,493
BEGIN DESCRIPTION:
LITTLE LLANO 067 9.0
END DESCRIPTION:
XS GIS Cut Line= 3
      2869555.68     10213053.07      2869505.25     10212570.00
      2869305.68     10212253.11
#Sta/Elev= 30
  4514.3  906.55  4665.1  902.35  4795.8  900.84  4866.2  898.87  4993.9  891.29
  4994.2  890.79  4997.9  891.29  5011.3  892.58  5020.0  896.27  5032.5  896.72
  5041.9  894.65  5047.8  895.70  5055.4  893.60  5078.4  895.54  5084.3  898.17
  5126.7  897.26  5157.3  899.11  5163.2  898.09  5185.4  898.74  5199.7  899.89
  5215.0  903.82  5230.3  903.31  5236.2  901.58  5244.5  901.94  5251.5  902.45
  5257.4  904.59  5272.7  906.92  5303.2  908.15  5352.2  912.72  5374.5  914.55
#Mann=4,-1,0
  4514.3    0.05       0  4993.9    0.05       0  4997.9    0.05       0
  5352.2    0.12       0
Bank Sta=4993.9,4997.9
Exp/Cntr=0.3,0.1

Type RM Length L Ch R = 1,3796,499,499,499
BEGIN DESCRIPTION:
LITTLE LLANO 067 8.0
END DESCRIPTION:
XS GIS Cut Line= 3
      2869705.71     10212853.08      2869993.50     10212557.00
      2869955.68     10212353.08
#Sta/Elev= 30
  4587.1  898.33  4657.7  894.70  4735.6  894.35  4763.9  892.88  4799.2  893.59
  4806.3  896.59  4813.3  894.06  4820.5  895.32  4827.4  893.76  4877.1  893.57
  4947.8  889.88  4954.8  890.31  4961.9  889.36  4968.9  890.23  4976.1  888.80
  4983.1  889.48  4990.2  887.07  4997.2  886.26  4997.5  885.76  5001.0  885.76
  5001.2  886.26  5024.3  886.69  5044.6  890.02  5054.8  890.72  5065.0  890.14
  5105.7  890.95  5136.2  894.11  5166.7  894.74  5180.9  896.19  5207.4  897.17
#Mann=3,-1,0
  4587.1    0.05       0  4997.2    0.05       0  5001.2    0.05       0
Bank Sta=4997.2,5001.2
Exp/Cntr=0.3,0.1

Type RM Length L Ch R = 1,3297,463,463,463
BEGIN DESCRIPTION:
LITTLE LLANO 067 7.0
END DESCRIPTION:
XS GIS Cut Line= 3
      2870405.68     10212903.10      2870254.50     10212599.00
      2870205.70     10212453.15
#Sta/Elev= 30
  4660.4  895.03  4663.2  895.03  4668.8  893.94  4691.2  891.99  4713.6  890.72
  4780.8  888.90  4825.6  888.60  4853.6  889.06  4876.0  888.76  4920.8  889.77
  4937.6  889.45  4960.0  890.01  4965.6  889.83  4982.4  885.00  4986.0  881.15
  4986.2  880.65  4989.7  880.65  4990.0  881.15  4994.9  881.91  5000.0  881.91
  5011.8  883.24  5017.0  885.00  5037.8  885.40  5048.6  886.58  5069.5  887.45
  5080.2  887.67  5101.1  887.08  5122.2  887.81  5143.3  891.99  5153.8  892.44
#Mann=3,-1,0
  4660.4    0.05       0  4986.0    0.05       0  4990.0    0.05       0
Bank Sta=4986,4990
Exp/Cntr=0.3,0.1

Type RM Length L Ch R = 1,2834,469,469,469
BEGIN DESCRIPTION:
LITTLE LLANO 067 6.0
END DESCRIPTION:
XS GIS Cut Line= 3
      2870455.68     10213003.12      2870514.25     10212447.00
      2870505.69     10212203.15
#Sta/Elev= 30
  4440.8  904.38  4460.9  903.37  4471.0  902.17  4481.0  902.00  4487.3  900.94
  4492.3  900.99  4551.4  897.98  4571.5  896.20  4580.3  895.02  4585.3  895.29
  4601.7  893.71  4662.0  889.36  4678.3  888.54  4722.4  887.18  4762.6  886.49
  4822.9  887.06  4967.3  885.23  4983.8  884.30  4993.9  882.00  4999.4  880.04
  5021.9  879.30  5022.2  878.80  5025.7  878.80  5025.9  879.30  5033.9  880.28
  5043.9  885.90  5053.9  888.44  5073.9  890.43  5144.0  891.67  5244.0  894.61
#Mann=3,-1,0
  4440.8    0.05       0  5021.9    0.05       0  5025.9    0.05       0
Bank Sta=5021.9,5025.9
Exp/Cntr=0.3,0.1

Type RM Length L Ch R = 1,2365,498,498,498
BEGIN DESCRIPTION:
LITTLE LLANO 067 5.0
END DESCRIPTION:
XS GIS Cut Line= 3
      2870605.71     10212853.09      2870725.50     10212761.00
      2870855.69     10212553.10
#Sta/Elev= 30
  4848.9  891.92  4906.0  887.17  4949.5  884.81  4962.4  881.26  4970.3  880.86
  4976.6  878.72  4984.8  879.07  4991.1  876.75  4995.0  876.51  4995.2  876.01
  4999.0  876.51  5012.5  876.64  5027.8  880.35  5043.1  881.63  5049.0  880.29
  5079.7  881.81  5085.6  880.90  5100.9  883.43  5106.8  883.05  5122.1  884.70
  5128.0  883.58  5137.4  884.70  5143.3  882.13  5164.5  884.96  5174.0  883.69
  5179.9  886.42  5195.2  885.80  5201.1  887.00  5216.4  886.34  5245.3  889.90
#Mann=3,-1,0
  4848.9    0.05       0  4995.0    0.03       0  4999.0    0.05       0
Bank Sta=4995,4999
Exp/Cntr=0.3,0.1

Type RM Length L Ch R = 1,1867,490,490,490
BEGIN DESCRIPTION:
LITTLE LLANO 067 4.0
END DESCRIPTION:
XS GIS Cut Line= 3
      2870805.68     10213103.11      2870850.50     10213046.00
      2871005.65     10212903.14
#Sta/Elev= 30
  4927.4  886.02  4934.6  885.86  4963.5  884.32  4978.0  882.19  4984.4  877.31
  4996.7  874.81  4996.9  874.31  5000.4  874.31  5000.7  874.81  5005.9  874.84
  5020.1  875.79  5026.9  876.00  5034.2  876.97  5041.1  878.57  5047.9  878.80
  5055.3  879.43  5062.1  879.57  5076.3  880.51  5083.6  881.39  5097.8  882.52
  5126.2  883.17  5140.3  884.14  5147.1  884.45  5154.5  884.48  5161.3  884.98
  5168.7  885.01  5175.5  885.56  5189.7  884.59  5197.1  884.33  5210.9  884.56
#Mann=3,-1,0
  4927.4    0.05       0  4996.7    0.05       0  5000.7    0.05       0
Bank Sta=4996.7,5000.7
Exp/Cntr=0.3,0.1

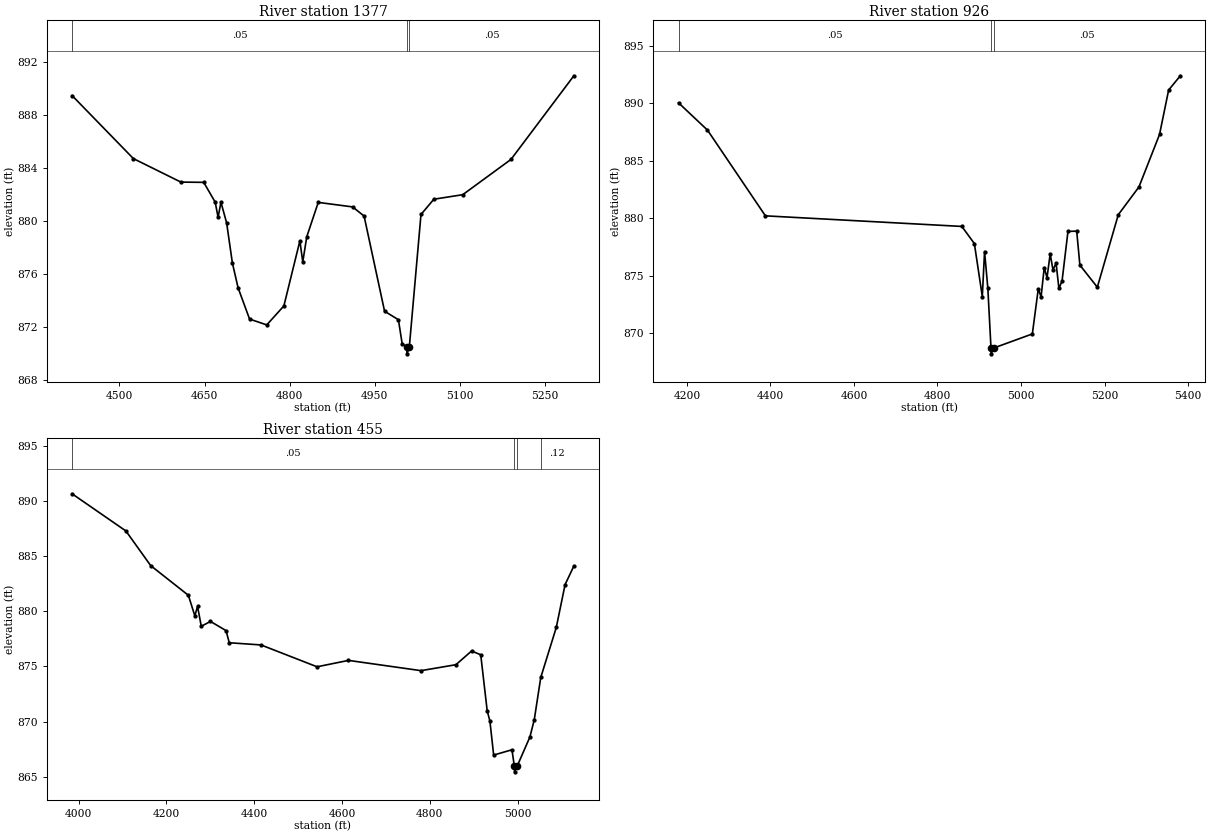
Type RM Length L Ch R = 1,1377,451,451,451
BEGIN DESCRIPTION:
LITTLE LLANO 067 3.0
END DESCRIPTION:
XS GIS Cut Line= 3
      2871105.69     10213703.08      2871185.00     10213125.00
      2871055.67     10212853.09
#Sta/Elev= 30
  4416.5  889.44  4524.6  884.69  4608.3  882.92  4648.6  882.90  4668.8  881.41
  4673.9  880.27  4679.0  881.40  4689.0  879.84  4699.1  876.83  4709.2  874.95
  4729.4  872.60  4759.7  872.16  4789.9  873.59  4818.1  878.49  4823.2  876.91
  4830.3  878.81  4850.5  881.39  4911.1  881.05  4931.3  880.36  4967.4  873.19
  4991.8  872.55  4998.4  870.75  5006.6  870.48  5006.9  869.98  5011.0  870.48
  5031.6  880.48  5054.3  881.63  5105.2  881.97  5190.3  884.63  5301.1  890.93
#Mann=3,-1,0
  4416.5    0.05       0  5006.6    0.05       0  5011.0    0.05       0
Bank Sta=5006.6,5011
Exp/Cntr=0.3,0.1

Type RM Length L Ch R = 1,926,471,471,471
BEGIN DESCRIPTION:
LITTLE LLANO 067 2.0
END DESCRIPTION:
XS GIS Cut Line= 3
      2871305.69     10213753.10      2871603.25     10212989.00
      2871855.69     10212703.10
#Sta/Elev= 30
  4180.0  890.02  4249.3  887.65  4388.0  880.20  4858.3  879.28  4888.3  877.79
  4907.3  873.19  4912.7  877.10  4920.5  873.93  4928.1  868.71  4928.6  868.21
  4934.2  868.71  5027.1  869.94  5041.3  873.86  5048.0  873.16  5055.6  875.71
  5062.2  874.82  5069.8  876.90  5076.4  875.52  5084.0  876.07  5090.7  873.89
  5098.2  874.53  5112.4  878.85  5133.3  878.87  5140.9  875.92  5182.7  874.00
  5232.9  880.30  5282.3  882.71  5331.6  887.27  5353.4  891.13  5381.4  892.37
#Mann=3,-1,0
  4180.0    0.05       0  4928.1    0.03       0  4934.2    0.05       0
Bank Sta=4928.1,4934.2
Exp/Cntr=0.3,0.1

Type RM Length L Ch R = 1,455,0,0,0
BEGIN DESCRIPTION:
LITTLE LLANO 067 1.0
END DESCRIPTION:
XS GIS Cut Line= 3
      2871455.67     10213853.13      2872050.75     10213031.00
      2872055.68     10212903.10
#Sta/Elev= 30
  3985.1  890.65  4107.7  887.28  4164.2  884.14  4250.0  881.45  4264.7  879.59
  4270.9  880.44  4279.4  878.64  4300.3  879.08  4335.8  878.25  4343.1  877.15
  4415.5  876.95  4543.1  874.97  4614.7  875.55  4779.8  874.62  4859.4  875.16
  4895.0  876.40  4915.9  876.06  4930.6  870.98  4936.8  870.05  4945.3  866.97
  4987.0  867.45  4992.5  865.95  4993.0  865.45  4998.7  865.95  5027.9  868.61
  5037.9  870.19  5052.6  874.00  5088.0  878.54  5108.0  882.42  5128.0  884.10
#Mann=4,-1,0
  3985.1    0.05       0  4992.5    0.03       0  4998.7    0.05       0
  5052.6    0.12       0
Bank Sta=4992.5,4998.7
Exp/Cntr=0.3,0.1

Chan Stop Cuts=-1