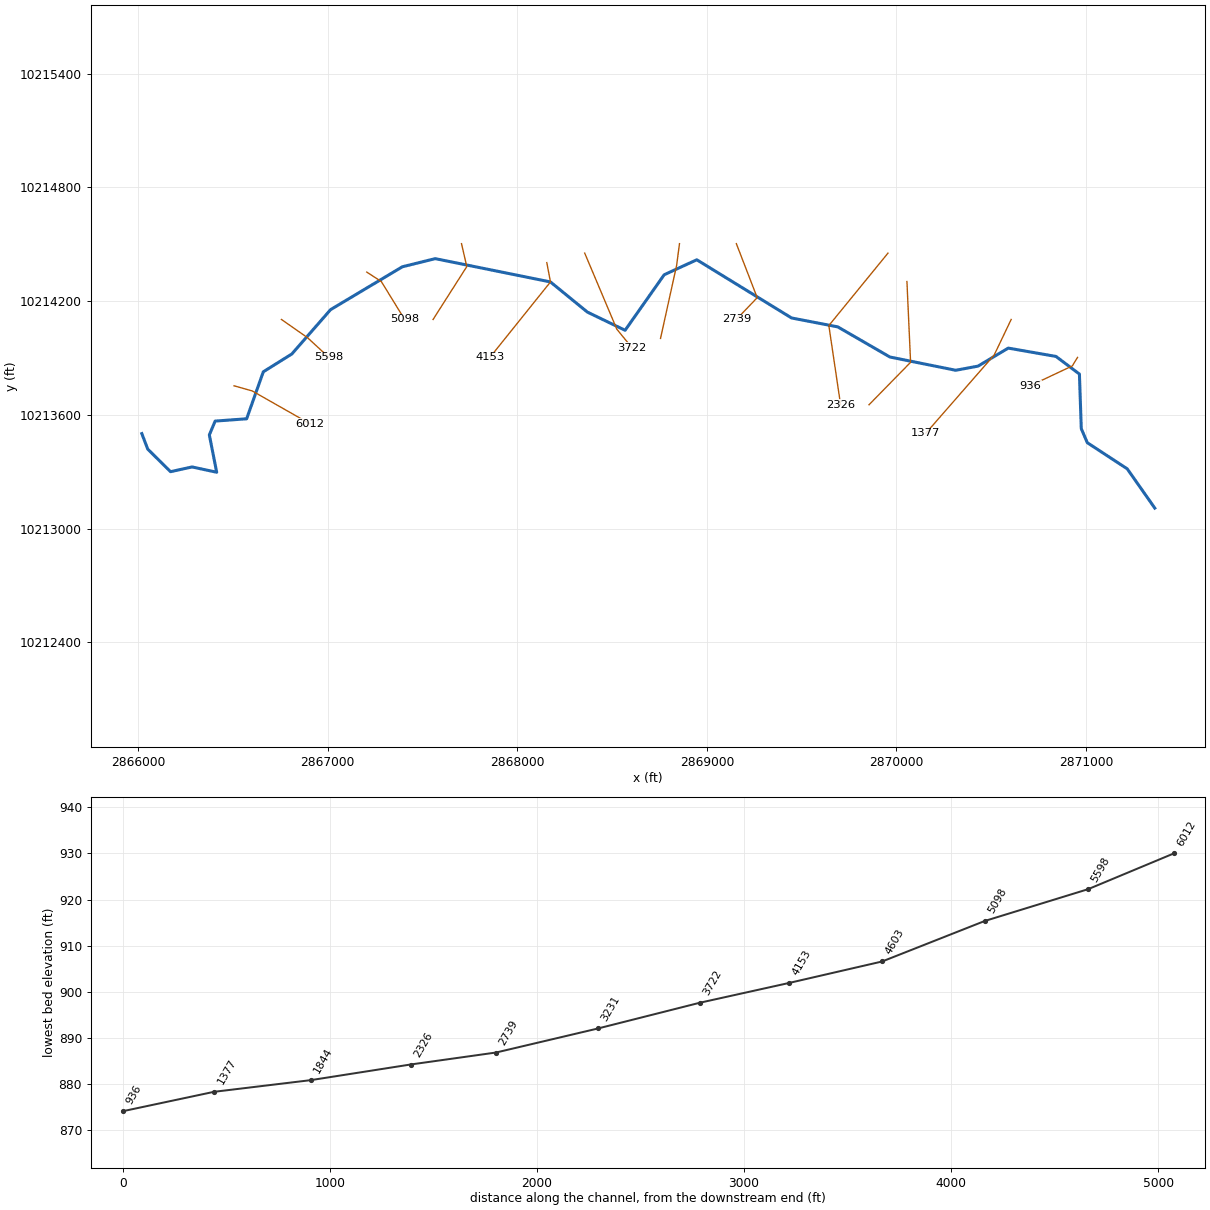
--- LITTLE LLANO 068.prj (project) ---

Proj Title=LITTLE LLANO 068 Base Level Engineering
Current Plan=p01
Default Exp/Contr=0.3,0.1
English Units
Geom File=g01
Flow File=f01
Plan File=p01
BEGIN DESCRIPTION:
LITTLE LLANO 068
END DESCRIPTION:

--- LITTLE LLANO 068.p01 (plan) ---

Plan Title=Multiple Run
Short Identifier=Multiple
Geom File=g01
Flow File=f01
Subcritical Flow
K Sum by GR= 0
Std Step Tol= 0.01
Critical Tol= 0.01
Num of Std Step Trials= 20
Max Error Tol= 0.3
Flow Tol Ratio= 0.001
Split Flow NTrial= 30
Split Flow Tol= 0.02
Split Flow Ratio= 0.02
Log Output Level= 0
Friction Slope Method= 1
Unsteady Friction Slope Method= 2
Unsteady Bridges Friction Slope Method= 1
Parabolic Critical Depth
Global Vel Dist=  1 , 1 , 1
Global Log Level= 0
CheckData=True
Encroach Param= -1, 0, 0, 0
BEGIN DESCRIPTION:
Multiple Run
END DESCRIPTION:

--- LITTLE LLANO 068.f01 (steady flow) ---

Flow Title=Multiple
Number of Profiles=7
Profile Names=10-year,25-year,50-year,1pct_min,100-year,1pct_plu,500-year
River Rch & RM= LITTLE LLANO 068,Reach-1,6012
     444     720    1440    1138    2021    3588    2933
River Rch & RM= LITTLE LLANO 068,Reach-1,5098
     591     984    1800    1319    2530    4852    3653
Boundary for River Rch & Prof#=LITTLE LLANO 068,Reach-1,1
Up Type=0
Dn Type=3
Dn Slope=0.005
Boundary for River Rch & Prof#=LITTLE LLANO 068,Reach-1,2
Up Type=0
Dn Type=3
Dn Slope=0.005
Boundary for River Rch & Prof#=LITTLE LLANO 068,Reach-1,3
Up Type=0
Dn Type=3
Dn Slope=0.005
Boundary for River Rch & Prof#=LITTLE LLANO 068,Reach-1,4
Up Type=0
Dn Type=3
Dn Slope=0.005
Boundary for River Rch & Prof#=LITTLE LLANO 068,Reach-1,5
Up Type=0
Dn Type=3
Dn Slope=0.005
Boundary for River Rch & Prof#=LITTLE LLANO 068,Reach-1,6
Up Type=0
Dn Type=3
Dn Slope=0.005
Boundary for River Rch & Prof#=LITTLE LLANO 068,Reach-1,7
Up Type=0
Dn Type=3
Dn Slope=0.005

--- LITTLE LLANO 068.g01 (geometry) ---

Geom Title=Existing Conditions

River Reach=LITTLE LLANO 068,Reach-1
Reach XY= 30
      2866019.00     10213501.00      2866050.25     10213419.00
      2866170.50     10213300.00      2866284.25     10213325.00
      2866414.00     10213297.00      2866375.25     10213494.00
      2866406.00     10213567.00      2866572.00     10213579.00
      2866660.00     10213827.00      2866810.50     10213921.00
      2867015.00     10214155.00      2867393.50     10214381.00
      2867567.00     10214424.00      2868175.00     10214301.00
      2868369.75     10214142.00      2868568.75     10214046.00
      2868775.00     10214339.00      2868947.00     10214418.00
      2869447.00     10214111.00      2869690.75     10214064.00
      2869965.75     10213905.00      2870313.25     10213835.00
      2870431.00     10213857.00      2870590.25     10213952.00
      2870842.00     10213908.00      2870965.75     10213815.00
      2870975.50     10213527.00      2871007.25     10213453.00
      2871218.00     10213315.00      2871363.25     10213108.00

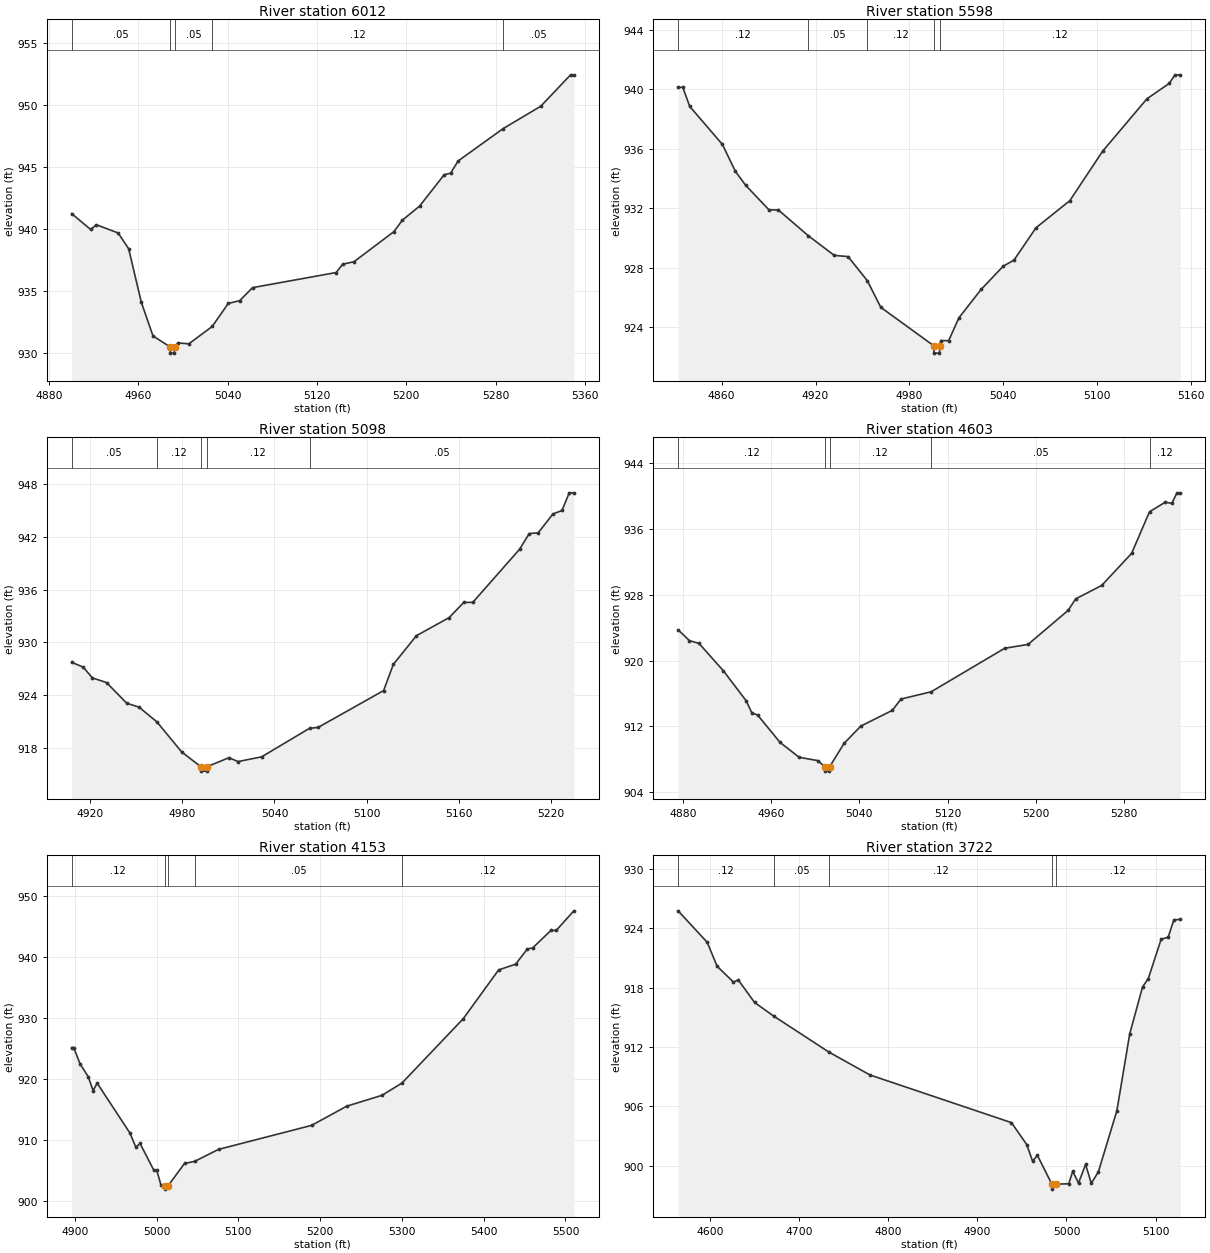
Type RM Length L Ch R = 1,6012,414,414,414
BEGIN DESCRIPTION:
LITTLE LLANO 068 12.0
END DESCRIPTION:
XS GIS Cut Line= 3
      2866505.66     10213753.12      2866601.50     10213726.00
      2866905.70     10213553.10
#Sta/Elev= 30
  4900.4  941.25  4917.4  939.97  4922.6  940.35  4942.0  939.69  4951.4  938.42
  4962.8  934.09  4973.2  931.39  4988.5  930.50  4988.8  930.00  4992.3  930.00
  4992.5  930.50  4995.7  930.82  5005.3  930.75  5026.2  932.15  5040.6  934.01
  5050.8  934.23  5062.3  935.28  5137.2  936.50  5143.0  937.17  5153.1  937.37
  5188.9  939.80  5196.4  940.72  5211.9  941.86  5233.8  944.38  5239.6  944.51
  5246.4  945.50  5286.4  948.09  5320.3  949.91  5347.0  952.44  5349.9  952.44
#Mann=5,-1,0
  4900.4    0.05       0  4988.5    0.05       0  4992.5    0.05       0
  5026.2    0.12       0  5286.4    0.05       0
Bank Sta=4988.5,4992.5
Exp/Cntr=0.3,0.1

Type RM Length L Ch R = 1,5598,500,500,500
BEGIN DESCRIPTION:
LITTLE LLANO 068 11.0
END DESCRIPTION:
XS GIS Cut Line= 3
      2866755.70     10214103.10      2866893.25     10214007.00
      2867005.70     10213903.10
#Sta/Elev= 30
  4832.2  940.12  4835.2  940.12  4839.6  938.84  4860.5  936.28  4868.8  934.47
  4875.4  933.53  4890.2  931.89  4896.3  931.87  4915.3  930.15  4932.0  928.82
  4940.8  928.74  4953.1  927.12  4961.7  925.33  4995.5  922.75  4995.7  922.25
  4999.2  922.25  4999.5  922.75  5000.0  923.09  5005.1  923.09  5011.6  924.62
  5025.8  926.53  5040.0  928.10  5046.8  928.50  5060.9  930.68  5082.5  932.50
  5103.5  935.83  5131.8  939.35  5146.0  940.38  5149.7  940.96  5153.1  940.96
#Mann=5,-1,0
  4832.2    0.12       0  4915.3    0.05       0  4953.1    0.12       0
  4995.5    0.07       0  4999.5    0.12       0
Bank Sta=4995.5,4999.5
Exp/Cntr=0.3,0.1

Type RM Length L Ch R = 1,5098,495,495,495
BEGIN DESCRIPTION:
LITTLE LLANO 068 10.0
END DESCRIPTION:
XS GIS Cut Line= 3
      2867205.71     10214353.10      2867282.75     10214303.00
      2867405.70     10214103.08
#Sta/Elev= 30
  4908.1  927.74  4915.6  927.19  4921.6  925.96  4930.8  925.43  4943.9  923.08
  4951.9  922.63  4963.5  920.96  4979.6  917.54  4992.1  915.84  4992.3  915.34
  4995.8  915.34  4996.1  915.84  5010.4  916.87  5016.3  916.43  5031.7  916.97
  5062.8  920.22  5068.4  920.32  5111.0  924.52  5117.3  927.50  5132.3  930.77
  5153.6  932.83  5163.1  934.56  5169.0  934.57  5199.4  940.62  5205.7  942.41
  5211.5  942.49  5221.1  944.64  5227.0  945.04  5231.7  947.05  5234.7  947.05
#Mann=5,-1,0
  4908.1    0.05       0  4963.5    0.12       0  4992.1    0.07       0
  4996.1    0.12       0  5062.8    0.05       0
Bank Sta=4992.1,4996.1
Exp/Cntr=0.3,0.1

Type RM Length L Ch R = 1,4603,450,450,450
BEGIN DESCRIPTION:
LITTLE LLANO 068 9.0
END DESCRIPTION:
XS GIS Cut Line= 3
      2867705.68     10214503.15      2867733.50     10214382.00
      2867555.66     10214103.07
#Sta/Elev= 30
  4875.7  923.76  4886.0  922.44  4894.6  922.11  4916.8  918.76  4937.3  915.14
  4942.6  913.64  4947.7  913.40  4968.1  910.06  4985.4  908.25  5002.3  907.85
  5008.8  907.07  5009.1  906.57  5012.7  906.57  5012.9  907.07  5026.1  909.95
  5041.3  912.05  5069.8  913.96  5077.7  915.34  5105.0  916.22  5171.6  921.51
  5192.8  921.98  5229.2  926.13  5235.9  927.51  5259.6  929.16  5286.7  933.06
  5302.9  938.12  5317.2  939.28  5323.1  939.14  5327.8  940.42  5330.8  940.42
#Mann=5,-1,0
  4875.7    0.12       0  5008.8    0.07       0  5012.9    0.12       0
  5105.0    0.05       0  5302.9    0.12       0
Bank Sta=5008.8,5012.9
Exp/Cntr=0.3,0.1

Type RM Length L Ch R = 1,4153,431,431,431
BEGIN DESCRIPTION:
LITTLE LLANO 068 8.0
END DESCRIPTION:
XS GIS Cut Line= 3
      2868155.69     10214403.09      2868175.00     10214301.00
      2867855.67     10213903.09
#Sta/Elev= 30
  4896.1  925.17  4898.6  925.17  4906.3  922.52  4916.4  920.38  4922.3  918.10
  4927.3  919.32  4967.3  911.14  4974.6  908.80  4979.7  909.42  4996.4  905.06
  5000.0  905.06  5005.3  902.61  5009.7  902.41  5009.9  901.91  5013.8  902.41
  5034.1  906.13  5046.5  906.47  5075.7  908.44  5189.6  912.39  5232.5  915.54
  5275.7  917.33  5300.1  919.35  5375.0  929.92  5418.2  937.93  5439.0  938.87
  5453.4  941.38  5459.8  941.54  5482.2  944.42  5488.6  944.41  5510.2  947.64
#Mann=5,-1,0
  4896.1    0.12       0  5009.7    0.07       0  5013.8    0.12       0
  5046.5    0.05       0  5300.1    0.12       0
Bank Sta=5009.7,5013.8
Exp/Cntr=0.3,0.1

Type RM Length L Ch R = 1,3722,491,491,491
BEGIN DESCRIPTION:
LITTLE LLANO 068 7.0
END DESCRIPTION:
XS GIS Cut Line= 3
      2868355.68     10214453.13      2868525.00     10214052.00
      2868605.67     10213953.13
#Sta/Elev= 30
  4564.6  925.75  4597.2  922.57  4608.3  920.15  4626.6  918.55  4632.0  918.77
  4650.3  916.49  4671.8  915.11  4733.7  911.47  4779.7  909.16  4938.3  904.34
  4955.4  902.13  4962.0  900.45  4967.4  901.03  4983.6  898.12  4983.9  897.62
  4987.8  898.12  5002.5  898.16  5007.0  899.42  5013.5  898.23  5021.4  900.12
  5027.8  898.21  5035.7  899.35  5056.5  905.55  5070.9  913.32  5085.3  918.06
  5091.7  918.90  5106.1  922.87  5114.0  923.09  5120.4  924.84  5127.6  924.88
#Mann=5,-1,0
  4564.6    0.12       0  4671.8    0.05       0  4733.7    0.12       0
  4983.6    0.07       0  4987.8    0.12       0
Bank Sta=4983.6,4987.8
Exp/Cntr=0.3,0.1

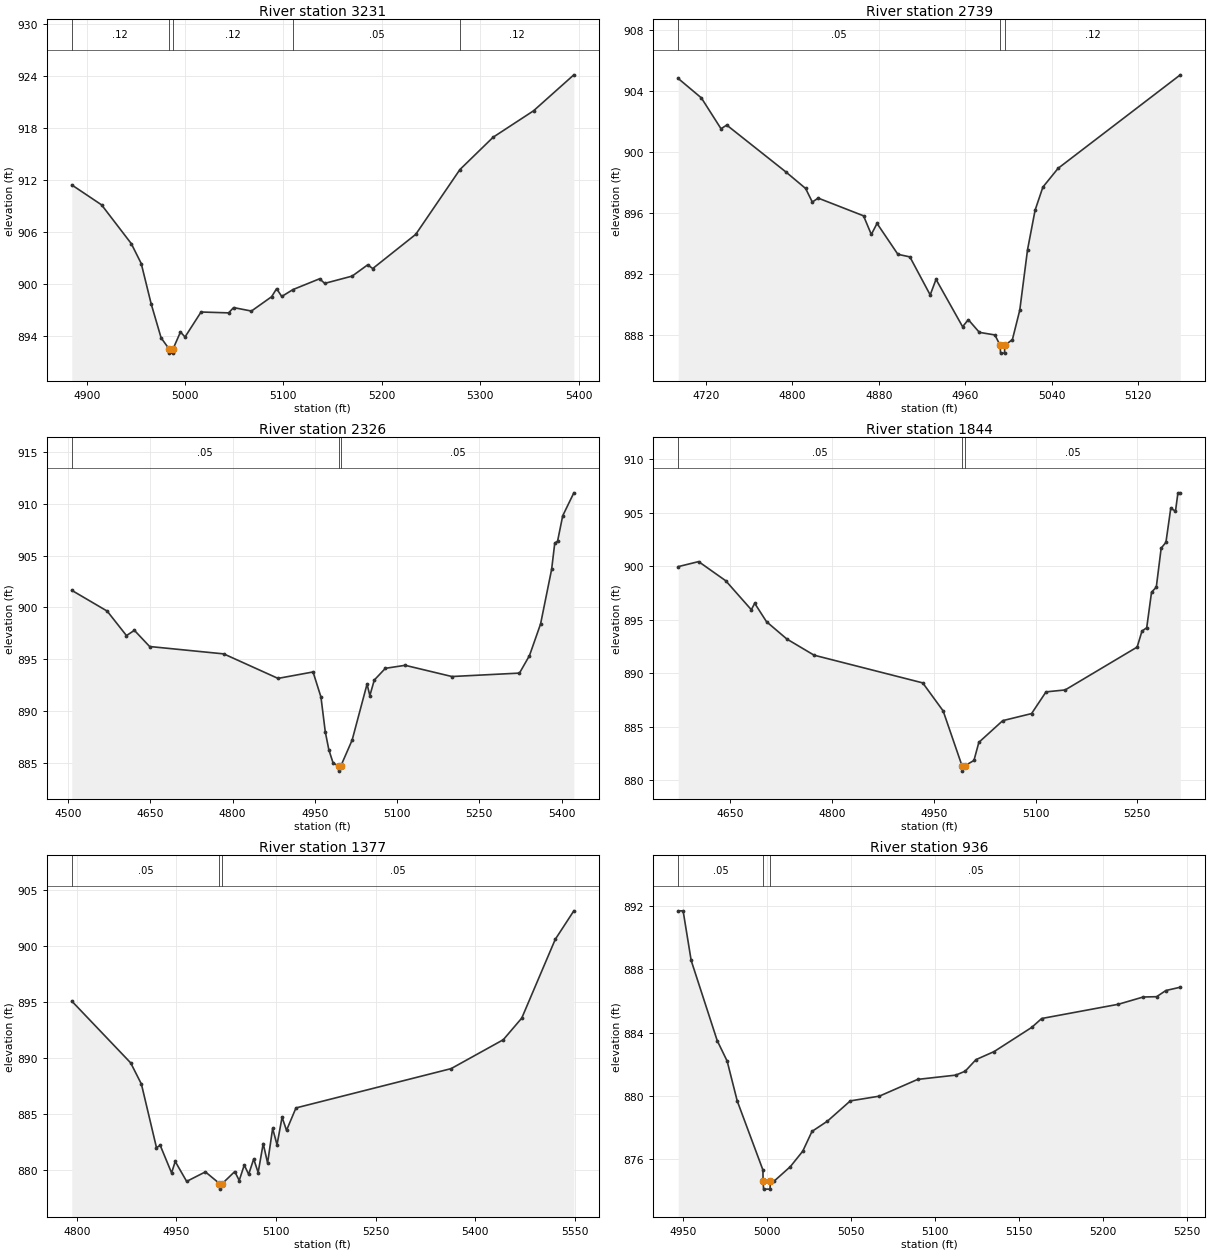
Type RM Length L Ch R = 1,3231,492,492,492
BEGIN DESCRIPTION:
LITTLE LLANO 068 6.0
END DESCRIPTION:
XS GIS Cut Line= 3
      2868855.69     10214503.13      2868840.75     10214389.00
      2868755.67     10214003.07
#Sta/Elev= 30
  4884.9  911.44  4915.2  909.14  4945.4  904.67  4955.5  902.38  4965.6  897.73
  4975.7  893.81  4983.7  892.55  4984.0  892.05  4987.6  892.05  4987.9  892.55
  4995.4  894.49  5000.0  893.91  5016.3  896.79  5044.3  896.69  5049.4  897.30
  5067.5  896.90  5088.0  898.55  5093.1  899.48  5098.3  898.58  5109.8  899.38
  5136.8  900.62  5142.0  900.09  5169.9  900.93  5185.7  902.23  5190.8  901.80
  5234.5  905.74  5279.4  913.21  5313.2  916.94  5354.2  919.98  5395.2  924.13
#Mann=5,-1,0
  4884.9    0.12       0  4983.7    0.07       0  4987.9    0.12       0
  5109.8    0.05       0  5279.4    0.12       0
Bank Sta=4983.7,4987.9
Exp/Cntr=0.3,0.1

Type RM Length L Ch R = 1,2739,413,413,413
BEGIN DESCRIPTION:
LITTLE LLANO 068 5.0
END DESCRIPTION:
XS GIS Cut Line= 3
      2869155.69     10214503.09      2869265.75     10214218.00
      2869155.69     10214103.11
#Sta/Elev= 30
  4694.4  904.82  4715.8  903.55  4734.0  901.53  4739.3  901.77  4793.9  898.71
  4812.3  897.62  4818.5  896.73  4823.9  896.99  4865.9  895.83  4873.1  894.61
  4878.4  895.33  4897.7  893.31  4908.8  893.14  4927.6  890.65  4933.0  891.67
  4957.6  888.57  4962.9  889.03  4973.1  888.20  4987.5  888.03  4992.4  887.34
  4992.7  886.84  4996.4  886.84  4996.6  887.34  5003.7  887.73  5010.5  889.65
  5017.7  893.61  5024.7  896.20  5031.9  897.71  5046.0  898.94  5159.1  905.06
#Mann=3,-1,0
  4694.4    0.05       0  4992.4    0.07       0  4996.6    0.12       0
Bank Sta=4992.4,4996.6
Exp/Cntr=0.3,0.1

Type RM Length L Ch R = 1,2326,482,482,482
BEGIN DESCRIPTION:
LITTLE LLANO 068 4.0
END DESCRIPTION:
XS GIS Cut Line= 3
      2869955.71     10214453.14      2869643.75     10214071.00
      2869705.69     10213653.07
#Sta/Elev= 30
  4506.7  901.65  4571.3  899.65  4606.5  897.29  4620.9  897.80  4648.7  896.24
  4783.9  895.53  4882.9  893.17  4946.8  893.79  4961.2  891.38  4969.1  888.03
  4975.6  886.30  4983.5  885.00  4993.3  884.74  4993.6  884.24  4997.5  884.74
  5018.1  887.23  5045.3  892.62  5050.4  891.51  5058.5  893.01  5078.7  894.14
  5114.8  894.43  5200.1  893.35  5323.3  893.68  5341.6  895.37  5361.8  898.41
  5382.0  903.68  5387.7  906.20  5392.8  906.38  5402.2  908.83  5422.5  911.04
#Mann=3,-1,0
  4506.7    0.05       0  4993.3    0.05       0  4997.5    0.05       0
Bank Sta=4993.3,4997.5
Exp/Cntr=0.3,0.1

Type RM Length L Ch R = 1,1844,467,467,467
BEGIN DESCRIPTION:
LITTLE LLANO 068 3.0
END DESCRIPTION:
XS GIS Cut Line= 3
      2870055.69     10214303.06      2870075.00     10213877.00
      2869855.69     10213653.12
#Sta/Elev= 30
  4573.5  899.97  4603.5  900.44  4643.5  898.65  4681.2  895.94  4686.2  896.54
  4703.6  894.82  4733.6  893.20  4773.7  891.69  4933.8  889.10  4963.9  886.48
  4991.7  881.35  4992.0  880.85  4996.0  881.35  5009.3  881.85  5016.5  883.54
  5051.7  885.57  5094.2  886.23  5115.5  888.26  5143.7  888.44  5249.8  892.45
  5256.9  893.94  5263.9  894.26  5271.0  897.58  5278.0  898.05  5285.2  901.70
  5292.2  902.24  5299.3  905.42  5306.3  905.16  5309.9  906.87  5313.4  906.87
#Mann=3,-1,0
  4573.5    0.05       0  4991.7    0.03       0  4996.0    0.05       0
Bank Sta=4991.7,4996
Exp/Cntr=0.3,0.1

Type RM Length L Ch R = 1,1377,441,441,441
BEGIN DESCRIPTION:
LITTLE LLANO 068 2.0
END DESCRIPTION:
XS GIS Cut Line= 3
      2870605.69     10214103.12      2870516.25     10213916.00
      2870155.66     10213503.09
#Sta/Elev= 30
  4792.6  895.11  4881.3  889.59  4897.4  887.70  4920.1  882.02  4925.7  882.23
  4942.8  879.77  4948.3  880.79  4965.5  879.01  4993.7  879.86  5014.9  878.82
  5015.2  878.32  5019.2  878.82  5037.9  879.89  5044.6  879.09  5052.2  880.47
  5058.8  879.64  5066.4  881.01  5073.1  879.80  5080.7  882.39  5087.3  880.65
  5094.9  883.74  5101.5  882.28  5109.1  884.74  5115.8  883.57  5130.0  885.57
  5363.5  889.08  5442.0  891.66  5469.8  893.59  5520.2  900.62  5548.2  903.17
#Mann=3,-1,0
  4792.6    0.05       0  5014.9    0.03       0  5019.2    0.05       0
Bank Sta=5014.9,5019.2
Exp/Cntr=0.3,0.1

Type RM Length L Ch R = 1,936,0,0,0
BEGIN DESCRIPTION:
LITTLE LLANO 068 1.0
END DESCRIPTION:
XS GIS Cut Line= 3
      2870955.68     10213903.11      2870928.25     10213858.00
      2870705.72     10213753.13
#Sta/Elev= 30
  4947.2  891.71  4950.1  891.71  4954.9  888.57  4970.4  883.50  4976.3  882.21
  4982.3  879.69  4997.6  875.32  4997.7  874.61  4998.0  874.11  5001.8  874.11
  5002.1  874.61  5004.2  874.61  5013.9  875.53  5021.3  876.51  5026.8  877.76
  5036.0  878.41  5049.6  879.69  5066.9  879.99  5089.7  881.05  5112.4  881.32
  5118.0  881.57  5124.4  882.30  5135.2  882.81  5157.6  884.34  5163.5  884.90
  5209.1  885.80  5223.9  886.26  5231.9  886.28  5237.4  886.67  5246.0  886.88
#Mann=3,-1,0
  4947.2    0.05       0  4997.7    0.05       0  5002.1    0.05       0
Bank Sta=4997.7,5002.1
Exp/Cntr=0.3,0.1

Chan Stop Cuts=-1