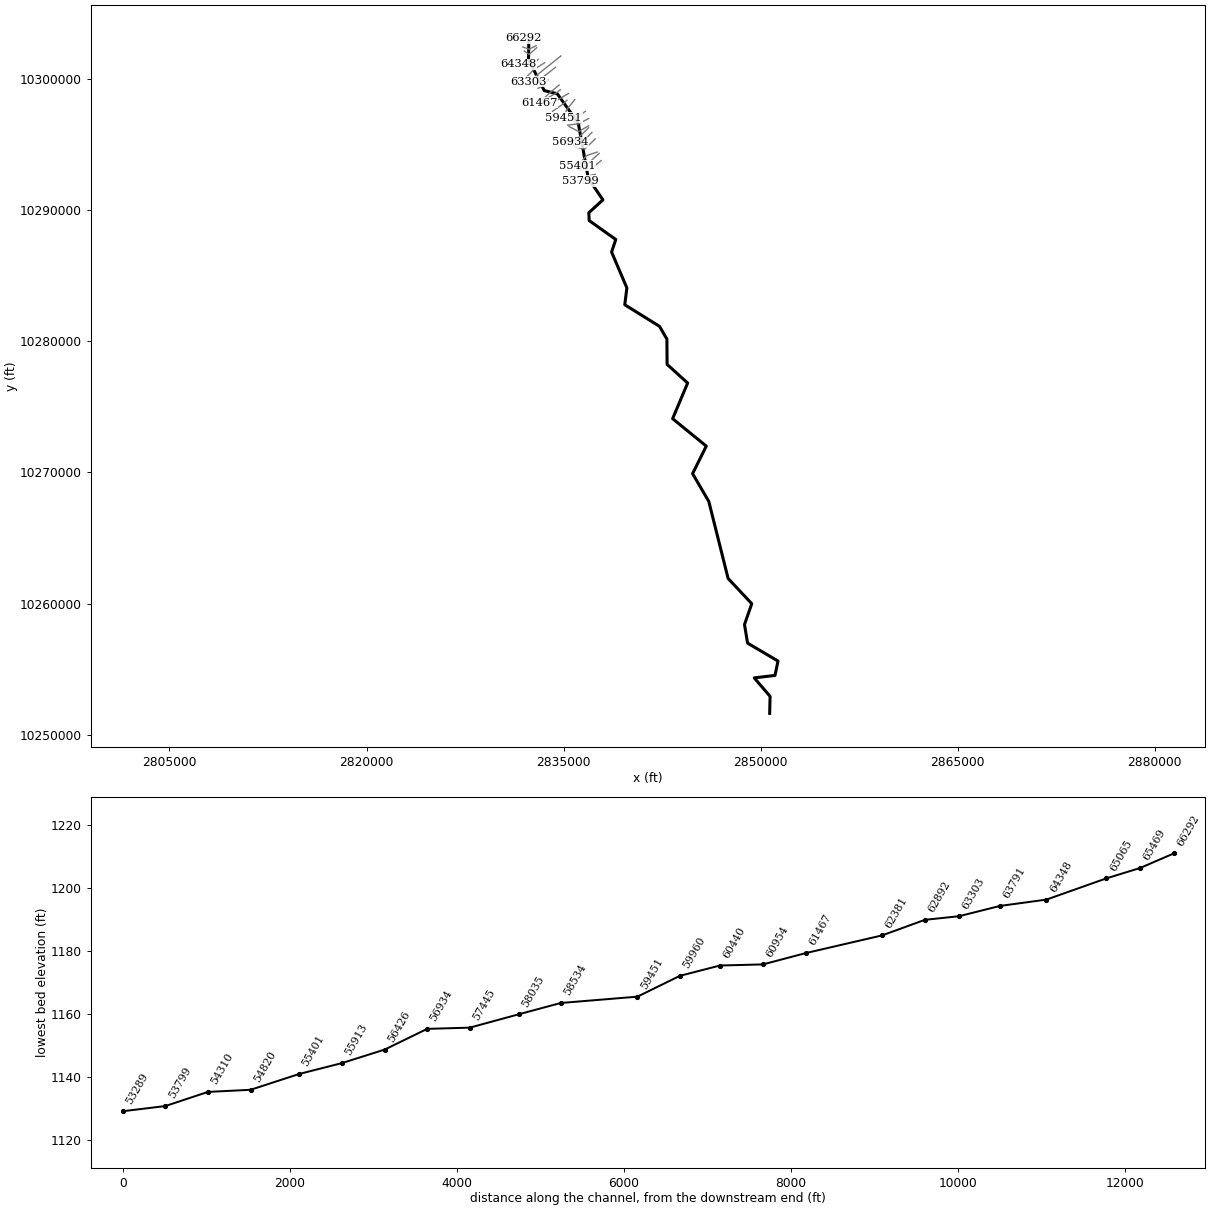
--- LITTLE LLANO RIVER.prj (project) ---

Proj Title=LITTLE LLANO RIVER Base Level Engineering
Current Plan=p01
Default Exp/Contr=0.3,0.1
English Units
Geom File=g01
Flow File=f01
Plan File=p01
Y Axis Title=Elevation
X Axis Title(PF)=Main Channel Distance
X Axis Title(XS)=Station
BEGIN DESCRIPTION:
LITTLE LLANO RIVER
END DESCRIPTION:
DSS Export Rating Curves= 0
DSS Export Rating Curve Sorted= 0
DSS Export Volume Flow Curves= 0
DXF OffsetX= 0
DXF OffsetY= 0
DXF ScaleX= 1
DXF ScaleY= 10

--- LITTLE LLANO RIVER.p01 (plan) ---

Plan Title=Multiple Run
Short Identifier=Multiple
Geom File=g01
Flow File=f01
Subcritical Flow
K Sum by GR= 0
Std Step Tol= 0.01
Critical Tol= 0.01
Num of Std Step Trials= 20
Max Error Tol= 0.3
Flow Tol Ratio= 0.001
Split Flow NTrial= 30
Split Flow Tol= 0.02
Split Flow Ratio= 0.02
Log Output Level= 0
Friction Slope Method= 1
Unsteady Friction Slope Method= 2
Unsteady Bridges Friction Slope Method= 1
Parabolic Critical Depth
Global Vel Dist=  1 , 1 , 1
Global Log Level= 0
CheckData=True
Encroach Param= -1, 0, 0, 0
BEGIN DESCRIPTION:
Multiple Run
END DESCRIPTION:

--- LITTLE LLANO RIVER.f01 (steady flow) ---

Flow Title=Multiple
Program Version=4.10
Number of Profiles= 7
Profile Names=10-year,25-year,50-year,1pct_min,100-year,1pct_plu,500-year
River Rch & RM=LITTLE LLANO RIV,Reach-1         ,66292
    1914    3408    5962    4170    8547   17518   11893
River Rch & RM=LITTLE LLANO RIV,Reach-1         ,64348
    2412    4376    7801    5448   11272   23323   15618
River Rch & RM=LITTLE LLANO RIV,Reach-1         ,60954
    2691    4935    8655    5952   12532   26386   17324
River Rch & RM=LITTLE LLANO RIV,Reach-1         ,56934
    3755    7040   12287    8511   17828   37344   24309
River Rch & RM=LITTLE LLANO RIV,Reach-1         ,55401
    4003    7532   12995    8877   18861   40074   25676
River Rch & RM=LITTLE LLANO RIV,Reach-1         ,51693
    4184    7899   13476    9030   19581   42459   26661
River Rch & RM=LITTLE LLANO RIV,Reach-1         ,45675
    4399    8328   14105    9368   20500   44861   27871
River Rch & RM=LITTLE LLANO RIV,Reach-1         ,42195
    4570    8677   14619    9574   21275   47279   28945
River Rch & RM=LITTLE LLANO RIV,Reach-1         ,36885
    4743    9018   15148    9892   22041   49111   29939
River Rch & RM=LITTLE LLANO RIV,Reach-1         ,36308
    4743    9018   15148    9892   22041   49111   29939
River Rch & RM=LITTLE LLANO RIV,Reach-1         ,35162
    6155   11741   19465   12587   28233   63330   37932
River Rch & RM=LITTLE LLANO RIV,Reach-1         ,28976
    6160   11754   19425   12509   28174   63460   37842
River Rch & RM=LITTLE LLANO RIV,Reach-1         ,27139
    7668   14603   23851   18617   34448   63738   45863
River Rch & RM=LITTLE LLANO RIV,Reach-1         ,22689
    7552   14395   23452   18373   33888   62505   45135
River Rch & RM=LITTLE LLANO RIV,Reach-1         ,18968
    7540   14372   23413   18348   33833   62386   45066
River Rch & RM=LITTLE LLANO RIV,Reach-1         ,18175
    8872   16847   27130   21047   39027   72368   51611
River Rch & RM=LITTLE LLANO RIV,Reach-1         ,16389
   11454   21571   34071   25988   48628   90991   63626
River Rch & RM=LITTLE LLANO RIV,Reach-1         ,15316
   11454   21571   34071   25988   48628   90991   63626
River Rch & RM=LITTLE LLANO RIV,Reach-1         ,11907
   11836   22257   34976   26670   49855   93196   65113
River Rch & RM=LITTLE LLANO RIV,Reach-1         ,6039
   11423   21496   33730   25843   48106   89547   62851
Boundary for River Rch & Prof#=LITTLE LLANO RIV,Reach-1         , 1
Up Type= 0
Dn Type= 3
Dn Slope=0.005
Boundary for River Rch & Prof#=LITTLE LLANO RIV,Reach-1         , 2
Up Type= 0
Dn Type= 3
Dn Slope=0.005
Boundary for River Rch & Prof#=LITTLE LLANO RIV,Reach-1         , 3
Up Type= 0
Dn Type= 3
Dn Slope=0.005
Boundary for River Rch & Prof#=LITTLE LLANO RIV,Reach-1         , 4
Up Type= 0
Dn Type= 3
Dn Slope=0.005
Boundary for River Rch & Prof#=LITTLE LLANO RIV,Reach-1         , 5
Up Type= 0
Dn Type= 3
Dn Slope=0.005
Boundary for River Rch & Prof#=LITTLE LLANO RIV,Reach-1         , 6
Up Type= 0
Dn Type= 3
Dn Slope=0.005
Boundary for River Rch & Prof#=LITTLE LLANO RIV,Reach-1         , 7
Up Type= 0
Dn Type= 3
Dn Slope=0.005
DSS Import GetInterval= 0
DSS Import GetPeak= 0
DSS Import FillOption= 0

--- LITTLE LLANO RIVER.g01 (geometry) ---

Geom Title=Existing Conditions
Program Version=4.10

River Reach=LITTLE LLANO RIV,Reach-1
Reach XY= 30
       2832357.5       10303059.       2832329.5       10301442.
      2833527.25       10299084.       2834520.5       10298838.
       2836119.5       10296602.        2836878.       10292399.
      2837992.75       10290760.      2836919.75       10289784.
       2836947.5       10289184.      2838971.75       10287743.
      2838652.25       10286791.       2839815.5       10284055.
      2839655.75       10282774.      2842301.75       10281128.
        2842862.       10280157.      2842877.75       10278231.
        2844442.       10276811.      2843298.25       10274097.
       2845859.5       10272007.      2844818.25       10269910.
       2846051.5       10267793.       2847522.5       10261924.
       2849322.5       10260006.       2848768.5       10258418.
      2849002.75       10257003.        2851319.       10255635.
      2851090.75       10254542.       2849509.5       10254355.
      2850715.75       10252949.       2850685.5       10251651.

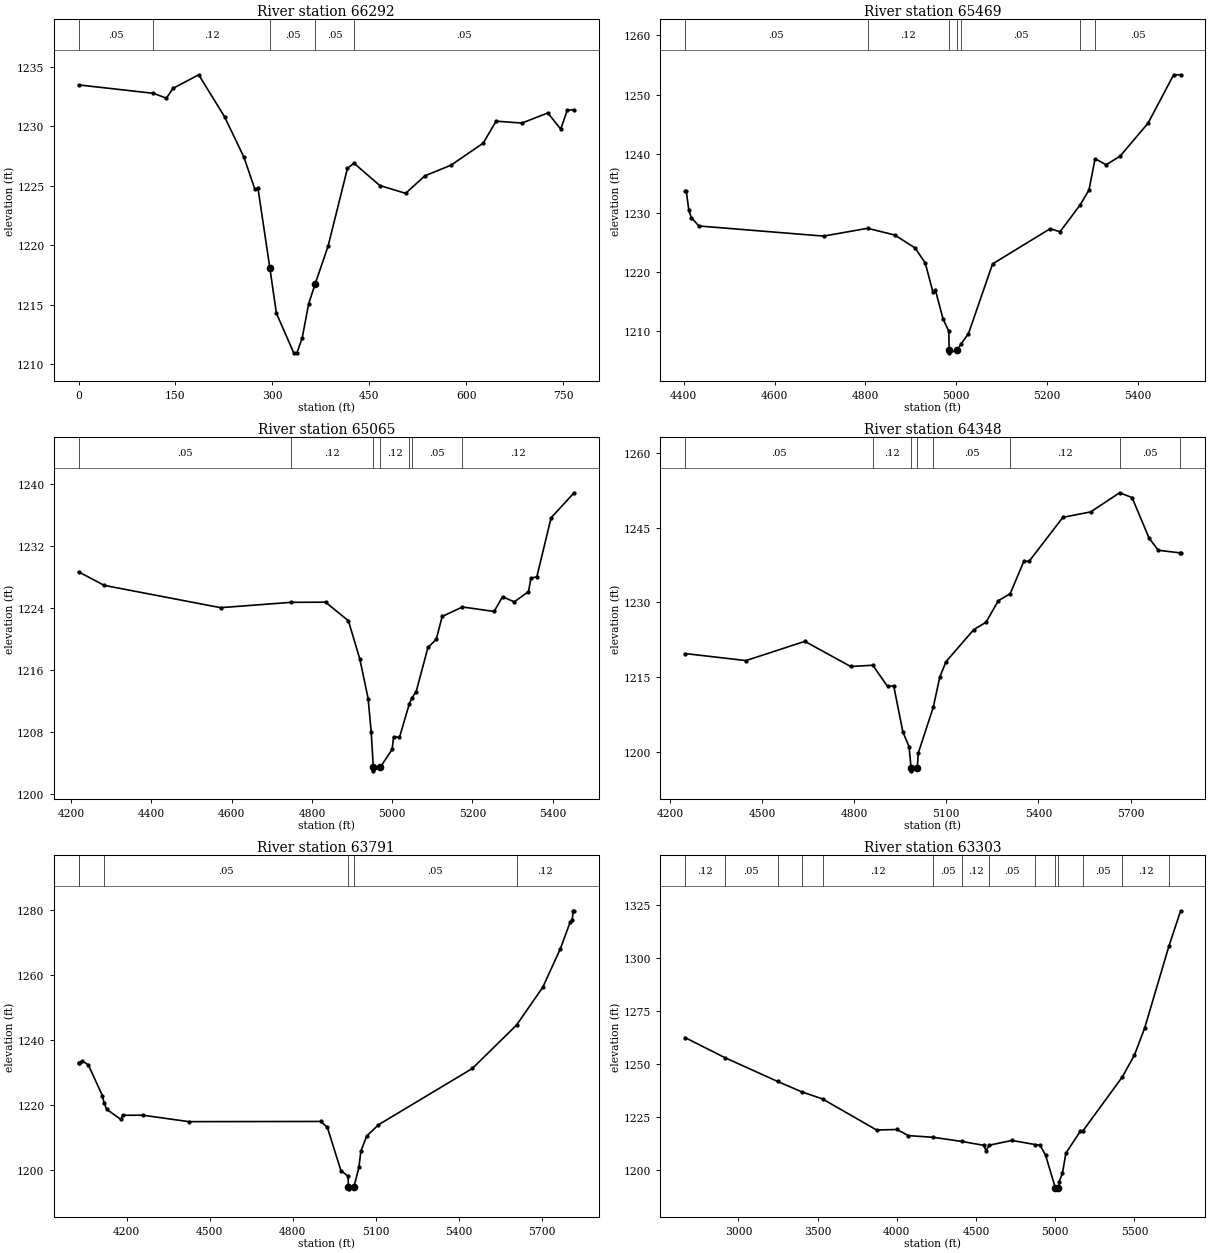
Type RM Length L Ch R = 1 ,66292   ,405,405,405
BEGIN DESCRIPTION:
LITTLE LLANO RIVER 125.0
END DESCRIPTION:
XS GIS Cut Line= 3
      2832691.68     10303063.75      2832356.89     10303056.87
      2831924.99     10303053.44
#Sta/Elev= 30
       0 1233.49     116 1232.78     136 1232.37     146 1233.19     186 1234.34
     226 1230.81     256  1227.4   272.7 1224.74   277.7 1224.78   296.1 1218.08
   306.1  1214.3     333 1210.96     338 1210.96   346.1 1212.21   356.1 1215.09
   366.1 1216.75   386.1 1219.92   416.1 1226.47   426.1 1226.91   466.1 1225.03
   506.1 1224.37   536.1 1225.85   576.1 1226.73   626.1 1228.59   646.1 1230.44
   686.1 1230.28   726.1 1231.13   746.1 1229.77   756.1 1231.35   766.8 1231.41
#Mann= 5 ,-1 , 0
       0     .05       0     116     .12       0   296.1     .05       0
   366.1     .05       0   426.1     .05       0
Bank Sta=296.1,366.1
XS Rating Curve= 0 ,0
Exp/Cntr=0.3,0.1

Type RM Length L Ch R = 1 ,65469   ,404,404,404
BEGIN DESCRIPTION:
LITTLE LLANO RIVER 124.0
END DESCRIPTION:
XS GIS Cut Line= 3
      2832905.64     10302503.09        2832371.       10302237.
      2831905.66     10302403.12
#Sta/Elev= 30
  4402.8 1233.68  4405.5 1233.68  4411.2 1230.44  4416.7 1229.17  4433.5 1227.78
  4707.8 1226.07  4804.9 1227.39  4864.6 1226.25  4909.4 1224.06  4931.8 1221.51
  4948.6 1216.61  4954.1 1216.95    4971 1212.04  4983.6 1209.98  4984.3 1206.83
  4984.8 1206.33  5002.3 1206.83  5010.8 1207.86  5026.9 1209.57    5080 1221.37
  5206.8 1227.32  5228.6 1226.81  5272.8 1231.34  5292.3 1233.87  5305.7 1239.16
    5330 1238.13  5360.8 1239.59  5422.4 1245.17  5478.7 1253.35  5494.1 1253.35
#Mann= 7 ,-1 , 0
  4402.8     .05       0  4804.9     .12       0  4984.3     .07       0
  5002.3     .12       0  5010.8     .05       0  5272.8     .12       0
  5305.7     .05       0
Bank Sta=4984.3,5002.3
XS Rating Curve= 0 ,0
Exp/Cntr=0.3,0.1

Type RM Length L Ch R = 1 ,65065   ,717,717,717
BEGIN DESCRIPTION:
LITTLE LLANO RIVER 123.0
END DESCRIPTION:
XS GIS Cut Line= 3
       2832955.7     10302353.13        2832371.       10301834.
      2832005.71     10302103.09
#Sta/Elev= 30
  4218.1 1228.73  4282.1 1226.98  4572.3  1224.1  4748.5 1224.79    4834 1224.81
  4890.9 1222.41  4919.3  1217.5  4940.2 1212.37  4947.8 1208.08    4953 1203.54
  4953.5 1203.04    4971 1203.54    5000 1205.82  5003.7 1207.45  5018.3 1207.35
    5043 1211.71  5048.7  1212.4    5060 1213.28  5089.3 1218.96  5110.1 1220.02
  5124.8 1222.97  5175.4 1224.19  5254.3 1223.61  5275.2 1225.51  5304.5 1224.85
  5339.9 1226.17  5346.2 1227.91  5360.8 1228.09  5396.3  1235.7  5453.7 1238.93
#Mann= 7 ,-1 , 0
  4218.1     .05       0  4748.5     .12       0    4953     .05       0
    4971     .12       0    5043     .12       0  5048.7     .05       0
  5175.4     .12       0
Bank Sta=4953,4971
XS Rating Curve= 0 ,0
Exp/Cntr=0.3,0.1

Type RM Length L Ch R = 1 ,64348   ,557,557,557
BEGIN DESCRIPTION:
Mapping XS 3736d8a2
END DESCRIPTION:
XS GIS Cut Line= 3
      2833070.52      10301468.1      2832723.28     10301164.27
      2831573.12     10301099.17
#Sta/Elev= 30
  4249.4 1219.78  4447.7 1218.37  4639.4 1222.22  4788.5 1217.19  4860.7 1217.44
  4908.7 1213.19  4928.7 1213.31  4958.8 1204.04  4978.8 1201.15  4985.4 1196.81
  4985.9 1196.31  5005.2 1196.81  5008.9 1199.91  5057.3    1209    5079 1215.12
    5099 1218.16  5189.2 1224.56  5229.2 1226.04  5269.3 1230.35    5308 1231.77
  5352.5 1238.26  5369.4 1238.23  5479.6 1247.04  5569.8 1248.12  5664.1 1251.95
  5704.8 1250.99  5760.1 1242.87  5790.1 1240.45  5861.5 1239.92  5862.8 1239.92
#Mann= 8 ,-1 , 0
  4249.4     .05       0  4860.7     .12       0  4985.4     .07       0
  5005.2     .12       0  5057.3     .05       0    5308     .12       0
  5664.1     .05       0  5861.5     .12       0
Bank Sta=4985.4,5005.2
XS Rating Curve= 0 ,0
Exp/Cntr=0.3,0.1

Type RM Length L Ch R = 1 ,63791   ,488,488,488
BEGIN DESCRIPTION:
LITTLE LLANO RIVER 120.0
END DESCRIPTION:
XS GIS Cut Line= 3
      2833555.71     10301203.13      2832732.25       10300682.
      2832155.71     10300103.13
#Sta/Elev= 30
  4025.5 1232.96  4026.2 1232.96  4039.1 1233.58    4061 1232.35    4112 1222.86
  4117.7 1220.75  4127.2 1218.71    4179 1215.59  4184.9 1216.88  4257.8  1216.9
  4424.8 1214.92  4901.3 1214.98  4924.9 1213.18    4974 1199.92    5000 1198.18
    5001  1194.8  5001.5  1194.3  5020.8  1194.8  5039.2 1200.92  5046.3 1205.89
  5067.5 1210.54  5109.9 1213.97  5449.3 1231.25  5608.9 1244.56  5703.9 1256.19
  5767.5 1268.02  5802.9  1276.2    5810 1276.77  5813.5 1279.64    5817 1279.64
#Mann= 6 ,-1 , 0
  4025.5     .05       0  4026.2     .12       0  4117.7     .05       0
    5001     .03       0  5020.8     .05       0  5608.9     .12       0
Bank Sta=5001,5020.8
XS Rating Curve= 0 ,0
Exp/Cntr=0.3,0.1

Type RM Length L Ch R = 1 ,63303   ,411,411,411
BEGIN DESCRIPTION:
LITTLE LLANO RIVER 119.0
END DESCRIPTION:
XS GIS Cut Line= 3
      2834789.69     10301720.04      2833407.33     10300616.59
      2832355.67      10299753.1
#Sta/Elev= 30
  2662.6  1262.4  2913.8 1252.95  3246.5 1241.72  3400.1 1236.79    3531 1233.44
  3872.4 1218.79  4000.5 1219.04  4072.5 1216.16  4230.6 1215.35  4411.1 1213.39
  4549.3 1211.56  4562.9 1209.12  4583.7 1211.63  4726.5 1213.88  4873.2 1211.94
  4903.7 1211.67  4938.9 1206.99  5000.7 1191.55  5001.2 1191.05  5020.6 1191.55
    5025 1194.33  5045.8 1198.46  5067.5 1207.85  5159.2 1218.26  5172.9 1218.16
  5424.2 1243.87  5500.7 1254.22  5564.6  1266.8  5717.9 1305.48  5792.1  1322.2
#Mann= 14 ,-1 , 0
  2662.6     .12       0  2913.8     .05       0  3246.5     .12       0
  3400.1     .05       0    3531     .12       0  4230.6     .05       0
  4411.1     .12       0  4583.7     .05       0  4873.2     .12       0
  5000.7     .07       0  5020.6     .12       0  5172.9     .05       0
  5424.2     .12       0  5717.9     .05       0
Bank Sta=5000.7,5020.6
XS Rating Curve= 0 ,0
Exp/Cntr=0.3,0.1

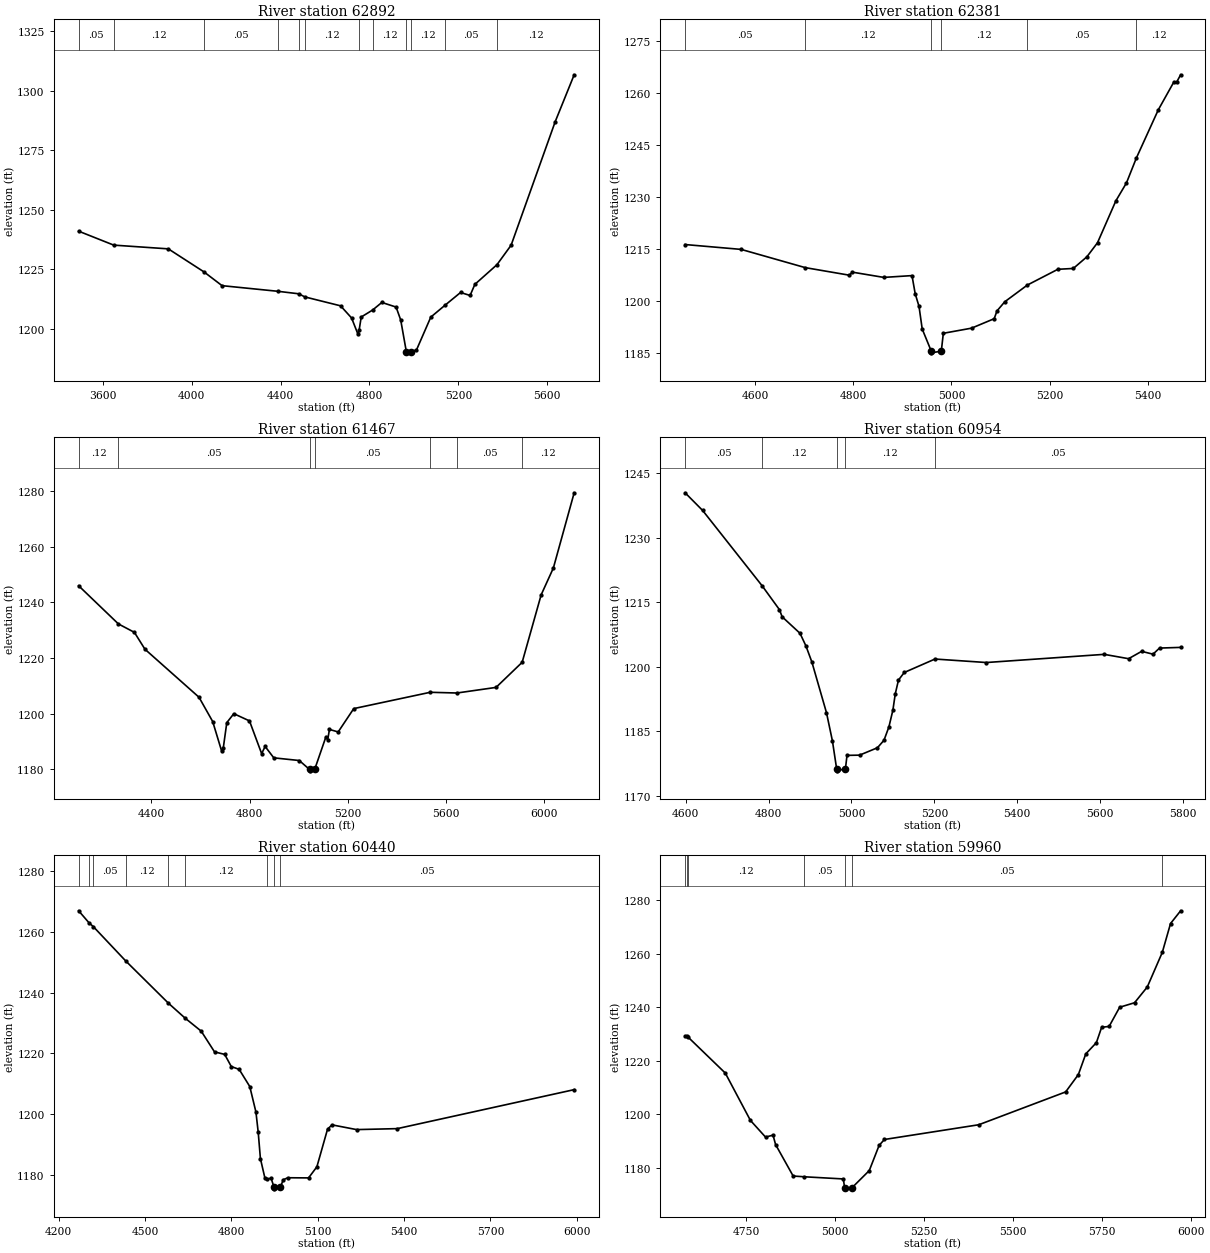
Type RM Length L Ch R = 1 ,62892   ,511,511,511
BEGIN DESCRIPTION:
LITTLE LLANO RIVER 118.0
END DESCRIPTION:
XS GIS Cut Line= 3
      2834383.63     10300861.86       2833204.5       10299921.
      2832655.68     10299453.11
#Sta/Elev= 30
  3491.5    1241  3649.5 1235.14  3895.1 1233.57  4055.1 1223.92  4136.9 1218.11
  4387.4 1215.75  4481.6  1214.7  4509.5 1213.38  4670.1 1209.64  4719.7 1204.53
  4748.6 1197.65  4753.9 1199.56    4763 1204.94  4814.4 1207.88  4855.8 1211.06
  4919.9 1209.12  4940.7  1203.7    4966 1190.39  4966.5 1189.89  4985.9 1190.39
  5011.6 1191.08  5076.1  1204.9    5141 1209.96    5210 1215.24  5252.9 1213.99
  5274.4 1218.66  5373.8 1226.92  5437.4 1235.09  5636.1 1287.06  5721.2  1306.7
#Mann= 12 ,-1 , 0
  3491.5     .05       0  3649.5     .12       0  4055.1     .05       0
  4387.4     .12       0  4481.6     .05       0  4509.5     .12       0
  4753.9     .05       0  4814.4     .12       0    4966     .07       0
  4985.9     .12       0    5141     .05       0  5373.8     .12       0
Bank Sta=4966,4985.9
XS Rating Curve= 0 ,0
Exp/Cntr=0.3,0.1

Type RM Length L Ch R = 1 ,62381   ,914,914,914
BEGIN DESCRIPTION:
LITTLE LLANO RIVER 117.0
END DESCRIPTION:
XS GIS Cut Line= 3
      2833805.69     10299903.12      2833461.25       10299484.
      2833055.67      10299253.1
#Sta/Elev= 30
  4457.5  1216.2  4571.6  1214.8  4702.2 1209.54  4791.9 1207.36  4798.3 1208.23
  4862.2 1206.72  4919.6 1207.24  4926.1 1202.02  4933.9 1198.36  4940.4 1191.83
  4958.8 1185.46  4959.3 1184.96  4979.3 1185.46  4983.4  1190.6  5040.9 1192.08
    5087 1194.81  5092.7 1197.06  5108.6  1199.7  5154.6 1204.52  5216.7 1209.06
  5248.1  1209.3  5275.7 1212.65  5297.4 1216.72  5334.8 1228.81  5356.4 1233.99
  5376.5 1241.15  5421.3 1255.09    5453 1263.12  5458.8 1263.12  5466.7 1265.17
#Mann= 6 ,-1 , 0
  4457.5     .05       0  4702.2     .12       0  4958.8     .07       0
  4979.3     .12       0  5154.6     .05       0  5376.5     .12       0
Bank Sta=4958.8,4979.3
XS Rating Curve= 0 ,0
Exp/Cntr=0.3,0.1

Type RM Length L Ch R = 1 ,61467   ,513,513,513
BEGIN DESCRIPTION:
LITTLE LLANO RIVER 115.0
END DESCRIPTION:
XS GIS Cut Line= 3
      2834655.67      10299503.1      2833964.75       10298932.
      2833155.65     10298153.08
#Sta/Elev= 30
  4103.6 1246.03  4265.7 1232.28  4330.9 1229.24  4373.9 1223.16  4594.1 1205.87
    4650  1197.1  4686.6 1186.42    4693 1187.51  4707.4 1196.71    4736 1199.94
  4799.9 1197.34  4849.4 1185.55  4863.7 1188.13  4898.9 1184.03  5002.8 1183.07
  5044.6 1179.85  5045.1 1179.35  5065.5 1179.85  5111.6 1191.66  5118.8 1190.62
  5125.8 1194.27  5161.3 1193.36  5224.8 1201.77  5536.5 1207.65  5645.1 1207.39
  5804.7 1209.41  5911.1 1218.45  5988.6 1242.77  6038.3 1252.43  6123.1 1279.53
#Mann= 7 ,-1 , 0
  4103.6     .12       0  4265.7     .05       0  5044.6     .03       0
  5065.5     .05       0  5536.5     .12       0  5645.1     .05       0
  5911.1     .12       0
Bank Sta=5044.6,5065.5
XS Rating Curve= 0 ,0
Exp/Cntr=0.3,0.1

Type RM Length L Ch R = 1 ,60954   ,514,514,514
BEGIN DESCRIPTION:
LITTLE LLANO RIVER 114.0
END DESCRIPTION:
XS GIS Cut Line= 3
      2834755.67      10299153.1        2834444.       10298900.
      2833755.72     10298503.13
#Sta/Elev= 30
  4598.5 1240.45  4640.9 1236.33  4784.5  1218.8  4826.2 1213.26  4832.7  1211.6
  4875.8 1207.76  4890.1 1204.83  4904.5 1201.07  4939.7  1189.3  4954.1 1182.71
  4964.2 1176.26  4964.7 1175.76  4985.5 1176.26  4989.3 1179.36  5019.6 1179.41
  5062.7 1181.13  5078.5 1182.87  5090.4 1185.98    5100 1189.87  5105.8 1193.69
  5113.5 1196.88  5127.4 1198.64  5201.6 1201.77  5325.6 1200.96    5610 1202.86
  5668.9 1201.85  5700.4 1203.56  5727.8  1202.9  5743.5 1204.32  5794.5 1204.48
#Mann= 5 ,-1 , 0
  4598.5     .05       0  4784.5     .12       0  4964.2     .07       0
  4985.5     .12       0  5201.6     .05       0
Bank Sta=4964.2,4985.5
XS Rating Curve= 0 ,0
Exp/Cntr=0.3,0.1

Type RM Length L Ch R = 1 ,60440   ,480,480,480
BEGIN DESCRIPTION:
Mapping XS 714aad33
END DESCRIPTION:
XS GIS Cut Line= 3
      2835370.86     10298863.93       2834502.8     10298343.09
      2833851.73     10298060.96
#Sta/Elev= 30
  4269.1 1266.94  4305.6 1262.93    4320 1261.74  4432.3 1250.47  4581.3  1236.5
    4639 1231.61    4695 1227.32  4741.3 1220.49  4776.6 1219.67  4799.6 1215.66
  4826.9 1214.74  4863.8 1209.09  4885.2 1200.68  4893.2 1193.96  4900.7 1185.39
  4916.3 1178.99  4922.4 1178.49  4937.6 1178.95  4948.3 1175.91  4948.8 1175.41
  4969.7 1175.91  4980.4 1178.42    4996 1179.06  5068.1 1179.01    5097 1182.67
    5134 1195.05  5149.5 1196.47    5235 1194.91  5376.4 1195.23    5991 1208.06
#Mann= 9 ,-1 , 0
  4269.1     .05       0  4305.6     .12       0    4320     .05       0
  4432.3     .12       0  4581.3     .05       0    4639     .12       0
  4922.4     .05       0  4948.3     .05       0  4969.7     .05       0
Bank Sta=4948.3,4969.7
XS Rating Curve= 0 ,0
Exp/Cntr=0.3,0.1

Type RM Length L Ch R = 1 ,59960   ,509,509,509
BEGIN DESCRIPTION:
LITTLE LLANO RIVER 112.0
END DESCRIPTION:
XS GIS Cut Line= 3
      2835255.71     10298353.13       2834954.5       10298057.
      2834155.65     10297503.09
#Sta/Elev= 30
  4577.6 1229.31  4581.6 1229.28  4586.2 1228.86  4690.7 1215.44  4761.4 1197.74
  4803.9  1191.5  4825.1 1192.22  4832.2 1188.71  4881.7 1176.93    4913 1176.65
  5022.9 1175.84  5026.4 1172.64  5026.9 1172.14  5047.9 1172.64  5095.9 1178.97
  5123.6  1188.4  5138.5  1190.6    5404 1196.11  5648.5 1208.39  5684.3 1214.88
  5705.2 1222.62    5735 1226.82  5749.8 1232.57  5770.8 1232.88  5800.5 1240.06
  5842.4 1241.74  5878.2 1247.63  5920.5 1260.59  5943.7 1271.38  5972.1 1276.14
#Mann= 7 ,-1 , 0
  4577.6     .12       0  4581.6     .05       0  4586.2     .12       0
    4913     .05       0  5026.4     .05       0  5047.9     .05       0
  5920.5     .12       0
Bank Sta=5026.4,5047.9
XS Rating Curve= 0 ,0
Exp/Cntr=0.3,0.1

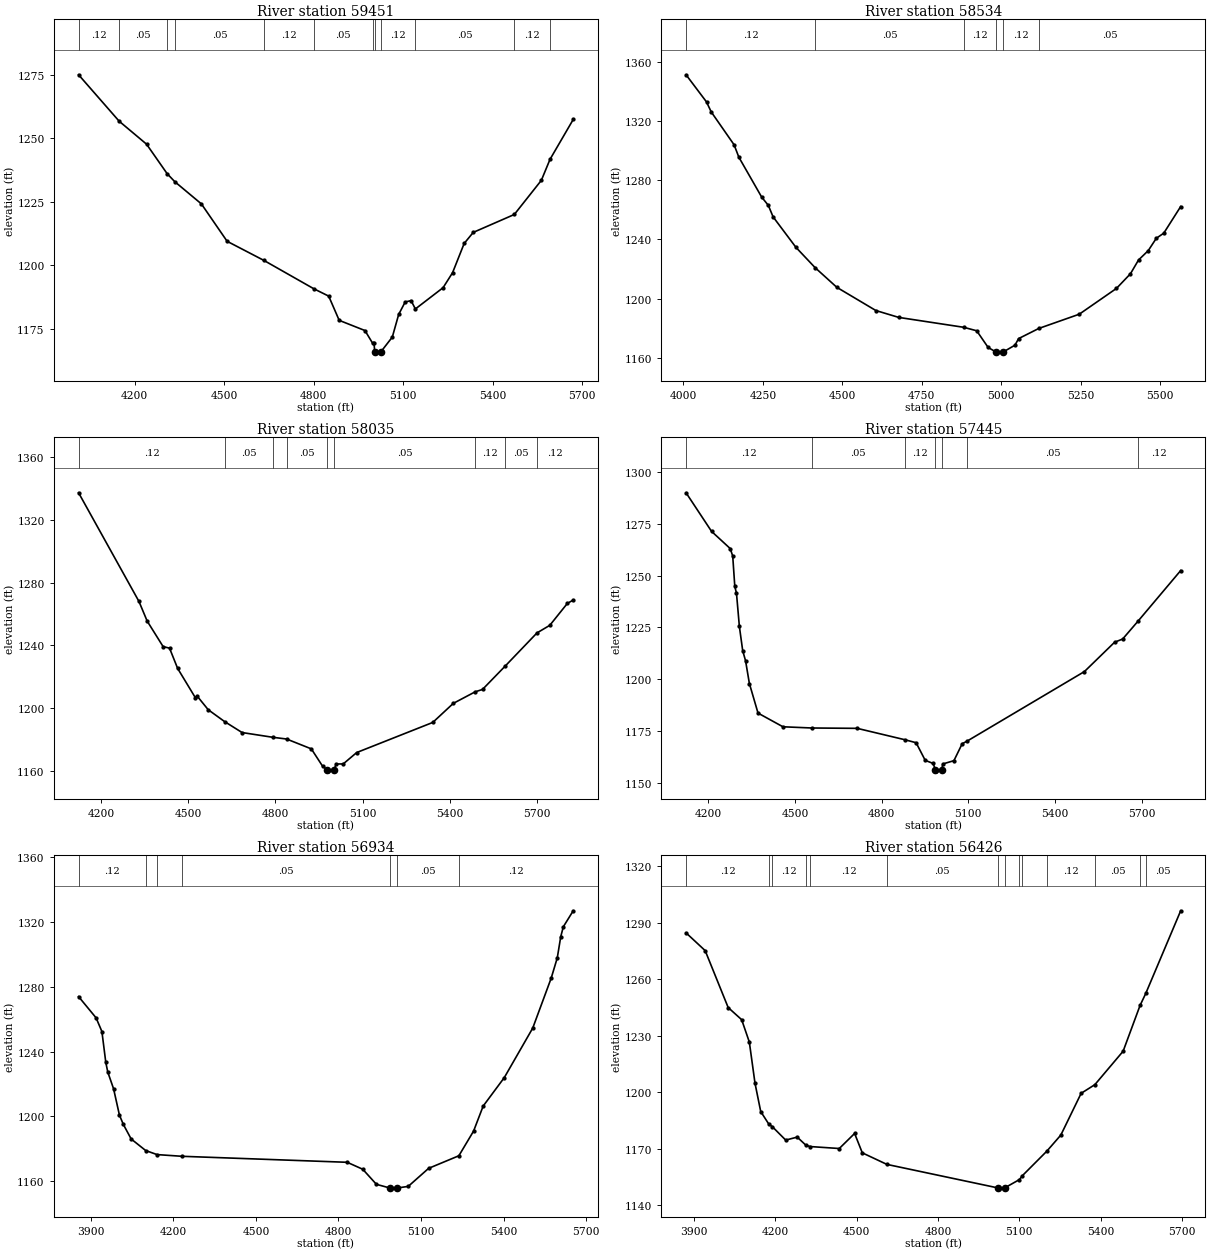
Type RM Length L Ch R = 1 ,59451   ,917,917,917
BEGIN DESCRIPTION:
LITTLE LLANO RIVER 111.0
END DESCRIPTION:
XS GIS Cut Line= 3
      2835855.67     10298403.09      2835235.75       10297633.
      2835005.68      10297003.1
#Sta/Elev= 30
  4011.4    1275  4147.6 1256.71  4239.3 1247.69  4308.4 1236.07  4334.3 1232.89
  4423.3 1224.17  4509.7 1209.44  4633.3  1201.9  4800.3 1190.77  4850.4 1187.86
  4885.6 1178.32    4972 1174.31    4998 1169.26  5002.6 1169.26  5004.6 1166.03
  5005.1 1165.53  5026.1 1166.03  5063.8 1171.74  5085.1 1180.64  5106.9 1185.55
  5126.8 1186.09  5141.1  1182.8  5234.1 1191.18    5266  1197.1  5304.8 1208.59
  5335.3 1212.95    5473    1220  5563.7 1233.44  5592.8 1241.71  5670.6  1257.4
#Mann= 12 ,-1 , 0
  4011.4     .12       0  4147.6     .05       0  4308.4     .12       0
  4334.3     .05       0  4633.3     .12       0  4800.3     .05       0
    4998     .12       0  5004.6     .07       0  5026.1     .12       0
  5141.1     .05       0    5473     .12       0  5592.8     .05       0
Bank Sta=5004.6,5026.1
XS Rating Curve= 0 ,0
Exp/Cntr=0.3,0.1

Type RM Length L Ch R = 1 ,58534   ,499,499,499
BEGIN DESCRIPTION:
LITTLE LLANO RIVER 109.0
END DESCRIPTION:
XS GIS Cut Line= 3
      2836655.65     10297503.09      2835836.25       10296945.
      2835305.68     10296753.11
#Sta/Elev= 30
  4008.6 1351.12  4072.9 1332.81  4087.8 1326.05  4159.7 1303.88  4174.6 1295.53
  4246.4 1268.61  4267.4 1262.99  4282.3 1255.28  4354.2 1234.69  4414.5 1220.99
  4482.9 1207.71  4605.6 1192.07  4677.4 1187.44  4881.9 1180.76  4922.7 1178.41
  4958.6 1167.17  4983.7 1164.03  4984.2 1163.53  5005.4 1164.03  5043.1 1168.71
  5054.4 1173.13  5117.9 1179.98  5245.2 1189.59  5362.2 1206.99  5406.2 1216.87
  5431.6 1226.16  5462.2 1232.49  5487.6 1240.83    5511 1244.26  5564.2 1262.23
#Mann= 6 ,-1 , 0
  4008.6     .12       0  4414.5     .05       0  4881.9     .12       0
  4983.7     .07       0  5005.4     .12       0  5117.9     .05       0
Bank Sta=4983.7,5005.4
XS Rating Curve= 0 ,0
Exp/Cntr=0.3,0.1

Type RM Length L Ch R = 1 ,58035   ,590,590,590
BEGIN DESCRIPTION:
LITTLE LLANO RIVER 108.0
END DESCRIPTION:
XS GIS Cut Line= 3
      2836905.68     10296953.11        2836125.       10296552.
      2835305.65     10296453.11
#Sta/Elev= 30
  4122.3 1337.29  4330.2 1267.99  4358.4 1255.49  4413.3 1239.21  4435.5  1238.2
  4463.3  1225.3  4524.3 1206.63  4529.9  1207.8  4568.6 1198.95  4624.8 1191.42
  4685.2  1184.4  4791.1 1181.37  4838.5 1180.27  4923.6 1173.99  4962.3 1162.97
  4979.3 1160.48  4979.8 1159.98    5001 1160.48  5009.4 1164.33  5033.5  1164.4
  5079.9 1171.65  5341.8 1190.85  5412.3 1202.98  5488.1  1210.4    5513 1211.88
  5592.1 1226.97  5700.6 1247.94  5744.7 1252.77  5805.1 1266.73  5825.3 1268.89
#Mann= 9 ,-1 , 0
  4122.3     .12       0  4624.8     .05       0  4791.1     .12       0
  4838.5     .05       0  4979.3     .05       0    5001     .05       0
  5488.1     .12       0  5592.1     .05       0  5700.6     .12       0
Bank Sta=4979.3,5001
XS Rating Curve= 0 ,0
Exp/Cntr=0.3,0.1

Type RM Length L Ch R = 1 ,57445   ,511,511,511
BEGIN DESCRIPTION:
LITTLE LLANO RIVER 107.0
END DESCRIPTION:
XS GIS Cut Line= 3
      2836905.69     10296403.11       2836145.5       10295965.
      2835405.72     10296353.09
#Sta/Elev= 30
  4122.6 1290.06  4210.9 1271.41  4275.6 1263.09  4284.2 1259.48  4291.4 1244.79
  4297.2 1241.55  4307.2 1225.48  4318.8 1213.72  4328.7 1208.87  4341.9  1197.9
  4371.8 1183.61  4458.1    1177  4558.2 1176.41  4715.2 1176.24  4879.4 1170.77
  4919.2  1169.3  4950.8 1160.77  4978.1 1159.29  4986.2 1156.21  4986.7 1155.71
  5007.9 1156.21  5011.7 1159.03  5050.2 1160.63  5078.8 1168.82  5094.7 1169.98
    5502 1203.67  5606.7 1217.87  5634.4 1219.39  5688.1  1228.1  5835.4 1252.48
#Mann= 7 ,-1 , 0
  4122.6     .12       0  4558.2     .05       0  4879.4     .12       0
  4986.2     .07       0  5007.9     .12       0  5094.7     .05       0
  5688.1     .12       0
Bank Sta=4986.2,5007.9
XS Rating Curve= 0 ,0
Exp/Cntr=0.3,0.1

Type RM Length L Ch R = 1 ,56934   ,508,508,508
BEGIN DESCRIPTION:
LITTLE LLANO RIVER 106.0
END DESCRIPTION:
XS GIS Cut Line= 3
      2836905.67      10296253.1        2836083.       10295458.
      2835505.67      10295153.1
#Sta/Elev= 30
  3855.9 1273.87  3919.5 1260.77  3940.6 1252.35  3954.8 1233.24    3962 1227.32
  3983.1 1216.98  4004.4 1200.74  4018.6 1195.02  4046.9 1186.07  4099.8 1178.93
    4141 1176.44  4231.7 1175.39  4831.8 1171.69  4888.3  1167.4    4938 1158.09
  4987.3 1155.82  4987.8 1155.32  5012.6 1155.82  5053.5 1156.83  5127.6 1167.96
  5237.5 1175.72    5291 1190.96  5325.8 1206.38  5402.5 1223.92  5505.9 1254.48
    5573 1285.31    5595 1297.77  5607.6 1310.84    5617 1316.96  5652.9 1326.81
#Mann= 7 ,-1 , 0
  3855.9     .12       0  4099.8     .05       0    4141     .12       0
  4231.7     .05       0  4987.3     .05       0  5012.6     .05       0
  5237.5     .12       0
Bank Sta=4987.3,5012.6
XS Rating Curve= 0 ,0
Exp/Cntr=0.3,0.1

Type RM Length L Ch R = 1 ,56426   ,513,513,513
BEGIN DESCRIPTION:
LITTLE LLANO RIVER 105.0
END DESCRIPTION:
XS GIS Cut Line= 3
      2837155.68      10295903.1        2836378.       10295083.
      2835705.65      10294903.1
#Sta/Elev= 30
  3869.8 1284.59  3940.4 1275.16  4025.3 1244.96  4075.1 1238.53  4103.4 1226.66
  4124.4 1204.75  4145.5 1189.76  4175.6 1183.05    4188 1181.79  4237.7 1174.63
  4280.2 1176.21    4313 1171.81  4329.1 1171.19  4435.5 1170.16  4492.1 1178.15
  4520.5 1167.86  4611.3 1161.73  5020.8 1149.26  5021.3 1148.76  5046.1 1149.26
  5100.8 1153.68  5110.8 1155.64  5201.9 1168.77  5253.5 1177.29  5328.5 1199.45
  5379.1 1204.04  5483.5 1221.79  5546.1 1246.11  5567.1 1252.46    5696 1296.31
#Mann= 14 ,-1 , 0
  3869.8     .12       0  4175.6     .05       0    4188     .12       0
    4313     .05       0  4329.1     .12       0  4611.3     .05       0
  5020.8     .05       0  5046.1     .05       0  5100.8     .12       0
  5110.8     .05       0  5201.9     .12       0  5379.1     .05       0
  5546.1     .12       0  5567.1     .05       0
Bank Sta=5020.8,5046.1
XS Rating Curve= 0 ,0
Exp/Cntr=0.3,0.1

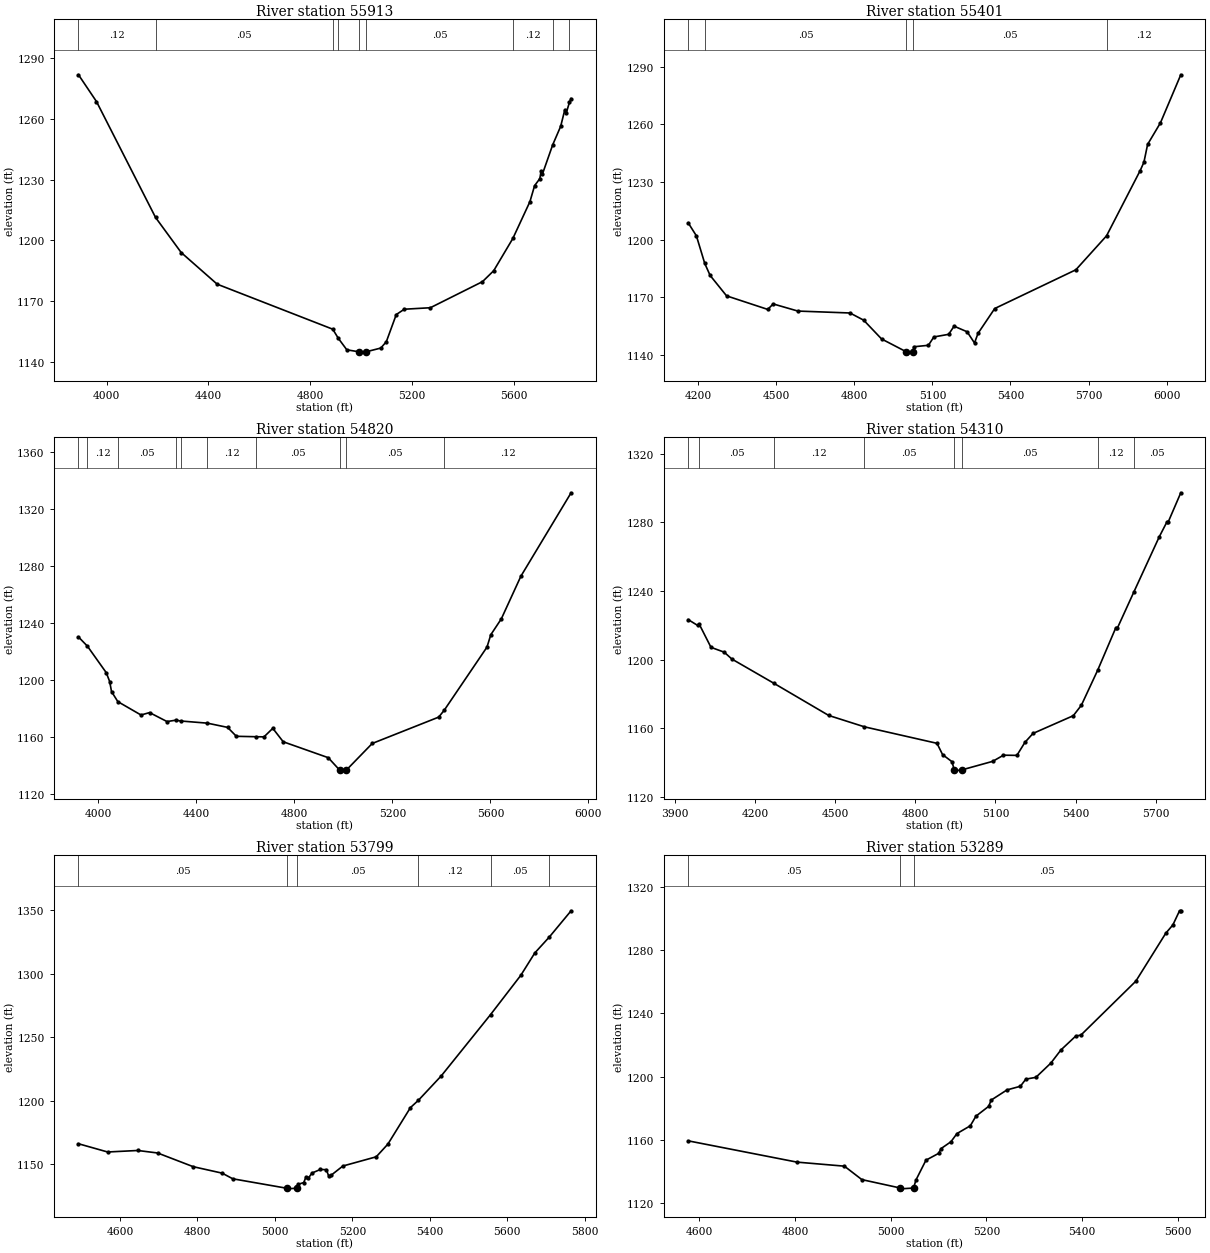
Type RM Length L Ch R = 1 ,55913   ,512,512,512
BEGIN DESCRIPTION:
LITTLE LLANO RIVER 104.0
END DESCRIPTION:
XS GIS Cut Line= 3
       2837405.7     10295403.13      2836610.75       10294628.
      2835805.67     10294803.11
#Sta/Elev= 30
  3889.7 1281.92  3960.4 1268.68  4192.3 1211.38  4292.9 1194.05  4434.3  1178.4
    4888 1156.15  4910.3 1151.56  4943.4 1145.94  4992.3 1144.96  4992.8 1144.46
  5018.6 1144.96  5076.8 1146.83  5098.5 1149.99  5137.4 1163.38  5168.9 1166.02
  5271.3 1166.76    5476 1179.65    5520 1185.06  5595.2 1201.01  5662.2 1219.19
  5680.6 1227.11  5701.1 1230.59  5706.2 1234.44  5711.4 1232.87  5751.7 1247.31
    5783 1256.45  5799.3 1264.68  5804.5 1262.95  5817.3 1268.24  5823.9 1270.16
#Mann= 9 ,-1 , 0
  3889.7     .12       0  4192.3     .05       0    4888     .12       0
  4910.3     .05       0  4992.3     .05       0  5018.6     .05       0
  5595.2     .12       0  5751.7     .05       0  5817.3     .12       0
Bank Sta=4992.3,5018.6
XS Rating Curve= 0 ,0
Exp/Cntr=0.3,0.1

Type RM Length L Ch R = 1 ,55401   ,581,581,581
BEGIN DESCRIPTION:
LITTLE LLANO RIVER 103.0
END DESCRIPTION:
XS GIS Cut Line= 3
       2837555.7     10294403.12        2836760.       10294138.
      2836055.66     10293353.09
#Sta/Elev= 30
  4161.3 1208.71  4192.9 1201.94  4225.1 1187.54  4245.7 1181.31  4308.9 1170.68
  4467.1 1163.62  4488.1 1166.47  4582.9 1162.76  4783.3 1161.76  4835.9 1158.01
  4904.6 1148.24  5000.3 1141.51  5000.8 1141.01  5026.9 1141.51  5027.8 1144.16
  5084.6 1144.94  5105.6 1149.28  5162.4 1150.65  5183.3 1154.89  5233.4 1151.98
  5261.8 1146.13  5275.3 1151.15  5339.5 1164.08  5651.3 1184.25  5769.3 1201.94
  5898.7 1235.95  5912.9 1240.26  5927.1 1249.54  5976.4 1260.76  6054.6 1285.79
#Mann= 5 ,-1 , 0
  4161.3     .12       0  4225.1     .05       0  5000.3     .03       0
  5026.9     .05       0  5769.3     .12       0
Bank Sta=5000.3,5026.9
XS Rating Curve= 0 ,0
Exp/Cntr=0.3,0.1

Type RM Length L Ch R = 1 ,54820   ,510,510,510
BEGIN DESCRIPTION:
LITTLE LLANO RIVER 102.0
END DESCRIPTION:
XS GIS Cut Line= 3
      2837705.68      10294303.1      2836905.75       10293576.
      2836105.66      10293103.1
#Sta/Elev= 30
    3919 1229.93  3955.4 1223.51  4032.2 1204.92  4046.4 1198.63  4053.8 1191.63
  4079.6 1184.57  4174.1 1175.19  4209.2 1176.88  4280.2 1170.59  4316.7 1171.56
  4336.8 1170.97  4445.2 1169.46  4527.5  1166.5  4563.3 1160.24  4643.3 1159.94
  4676.1 1159.85    4712 1165.83  4754.5  1156.4  4938.3 1145.23  4984.9  1136.5
  4985.4    1136    5012  1136.5  5117.9 1155.22  5389.1 1173.71  5411.9  1178.6
  5586.1 1222.83  5601.7 1231.52  5644.6 1242.66  5724.5  1272.6  5929.4 1331.14
#Mann= 10 ,-1 , 0
    3919     .05       0  3955.4     .12       0  4079.6     .05       0
  4316.7     .12       0  4336.8     .05       0  4445.2     .12       0
  4643.3     .05       0  4984.9     .05       0    5012     .05       0
  5411.9     .12       0
Bank Sta=4984.9,5012
XS Rating Curve= 0 ,0
Exp/Cntr=0.3,0.1

Type RM Length L Ch R = 1 ,54310   ,511,511,511
BEGIN DESCRIPTION:
LITTLE LLANO RIVER 101.0
END DESCRIPTION:
XS GIS Cut Line= 3
      2837855.71     10293753.13      2837044.75       10293086.
      2836255.69     10293003.11
#Sta/Elev= 30
  3949.9 1223.38  3985.8 1219.95  3990.8 1220.87  4035.3 1207.23  4084.8 1204.42
  4113.5 1200.41  4271.5 1186.23  4475.8 1167.58  4609.4 1160.96  4881.1 1151.35
    4902 1144.77  4937.1 1140.66  4945.8 1135.83  4946.3 1135.33  4972.9 1135.83
  5089.6 1140.86  5129.8 1144.44  5180.1 1144.33  5210.2 1151.93  5240.4 1157.11
  5391.2 1167.44  5421.4 1173.53    5482 1193.78  5550.6 1218.77  5555.6 1218.26
    5618 1239.53    5713 1271.64  5741.8 1280.33  5746.9 1280.42  5793.4 1297.22
#Mann= 8 ,-1 , 0
  3949.9     .12       0  3990.8     .05       0  4271.5     .12       0
  4609.4     .05       0  4945.8     .03       0  4972.9     .05       0
    5482     .12       0    5618     .05       0
Bank Sta=4945.8,4972.9
XS Rating Curve= 0 ,0
Exp/Cntr=0.3,0.1

Type RM Length L Ch R = 1 ,53799   ,510,510,510
BEGIN DESCRIPTION:
LITTLE LLANO RIVER 100.0
END DESCRIPTION:
XS GIS Cut Line= 3
      2837405.66     10292703.11      2836909.25       10292600.
      2836255.72     10292203.13
#Sta/Elev= 30
    4493 1166.26  4568.2 1159.79  4646.2 1160.97  4697.2 1159.01  4789.2 1148.24
  4863.8 1143.17  4891.3 1138.73    5030 1131.34  5030.5 1130.84  5057.3 1131.34
  5059.1 1134.34  5074.4 1135.75  5080.5 1140.32  5086.3 1139.24  5095.9 1143.28
  5117.3 1146.06  5132.8 1145.89  5138.6 1141.11  5144.6 1141.39  5175.4 1148.76
  5261.6 1156.01  5291.7    1166  5349.9 1194.66  5370.6 1200.46  5429.3 1219.53
  5556.7 1267.74  5634.8 1298.61    5671 1316.21  5708.4 1328.69  5764.6  1349.3
#Mann= 6 ,-1 , 0
    4493     .05       0    5030     .03       0  5057.3     .05       0
  5370.6     .12       0  5556.7     .05       0  5708.4     .12       0
Bank Sta=5030,5057.3
XS Rating Curve= 0 ,0
Exp/Cntr=0.3,0.1

Type RM Length L Ch R = 1 ,53289   ,512,512,512
BEGIN DESCRIPTION:
LITTLE LLANO RIVER 99.0
END DESCRIPTION:
XS GIS Cut Line= 3
      2837355.67      10292503.1      2837086.25       10292177.
      2836505.73     10292003.13
#Sta/Elev= 30
    4577 1159.53  4804.3 1146.08  4903.3 1143.53  4939.8 1135.03  5020.4  1129.7
  5020.9  1129.2  5047.8  1129.7  5052.8 1134.77  5073.7 1147.31  5100.2 1151.61
  5105.4 1154.66  5125.9 1158.96  5138.5 1164.13  5166.4 1169.05  5178.1 1175.11
  5204.7 1181.32  5209.9 1185.26    5243 1191.71  5270.9    1194  5282.4 1198.52
  5303.3 1199.64  5334.6 1208.65  5355.5 1216.91  5386.8 1225.79  5397.3 1226.32
  5512.1 1260.41  5574.7 1290.73  5589.5 1295.96  5603.4 1304.89    5606 1304.89
#Mann= 3 ,-1 , 0
    4577     .05       0  5020.4     .05       0  5047.8     .05       0
Bank Sta=5020.4,5047.8
XS Rating Curve= 0 ,0
Exp/Cntr=0.3,0.1