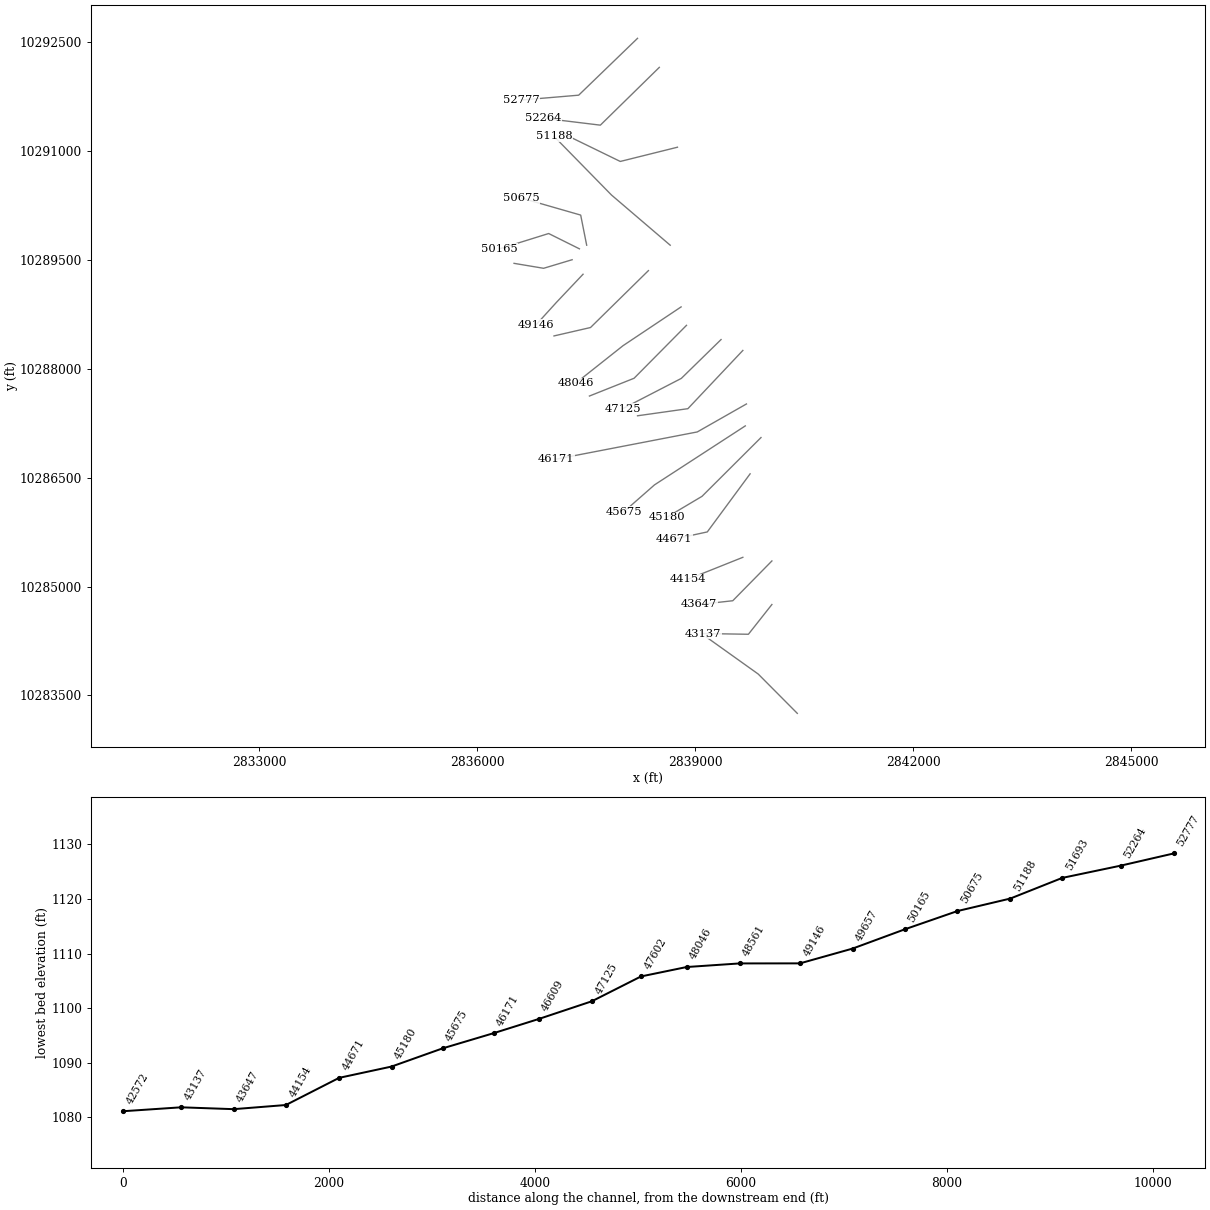
HEC-RAS study LITTLE LLANO RIVER.prj: LITTLE LLANO RIVER Base Level Engineering

--- LITTLE LLANO RIVER.g01 (geometry) --- (continued)

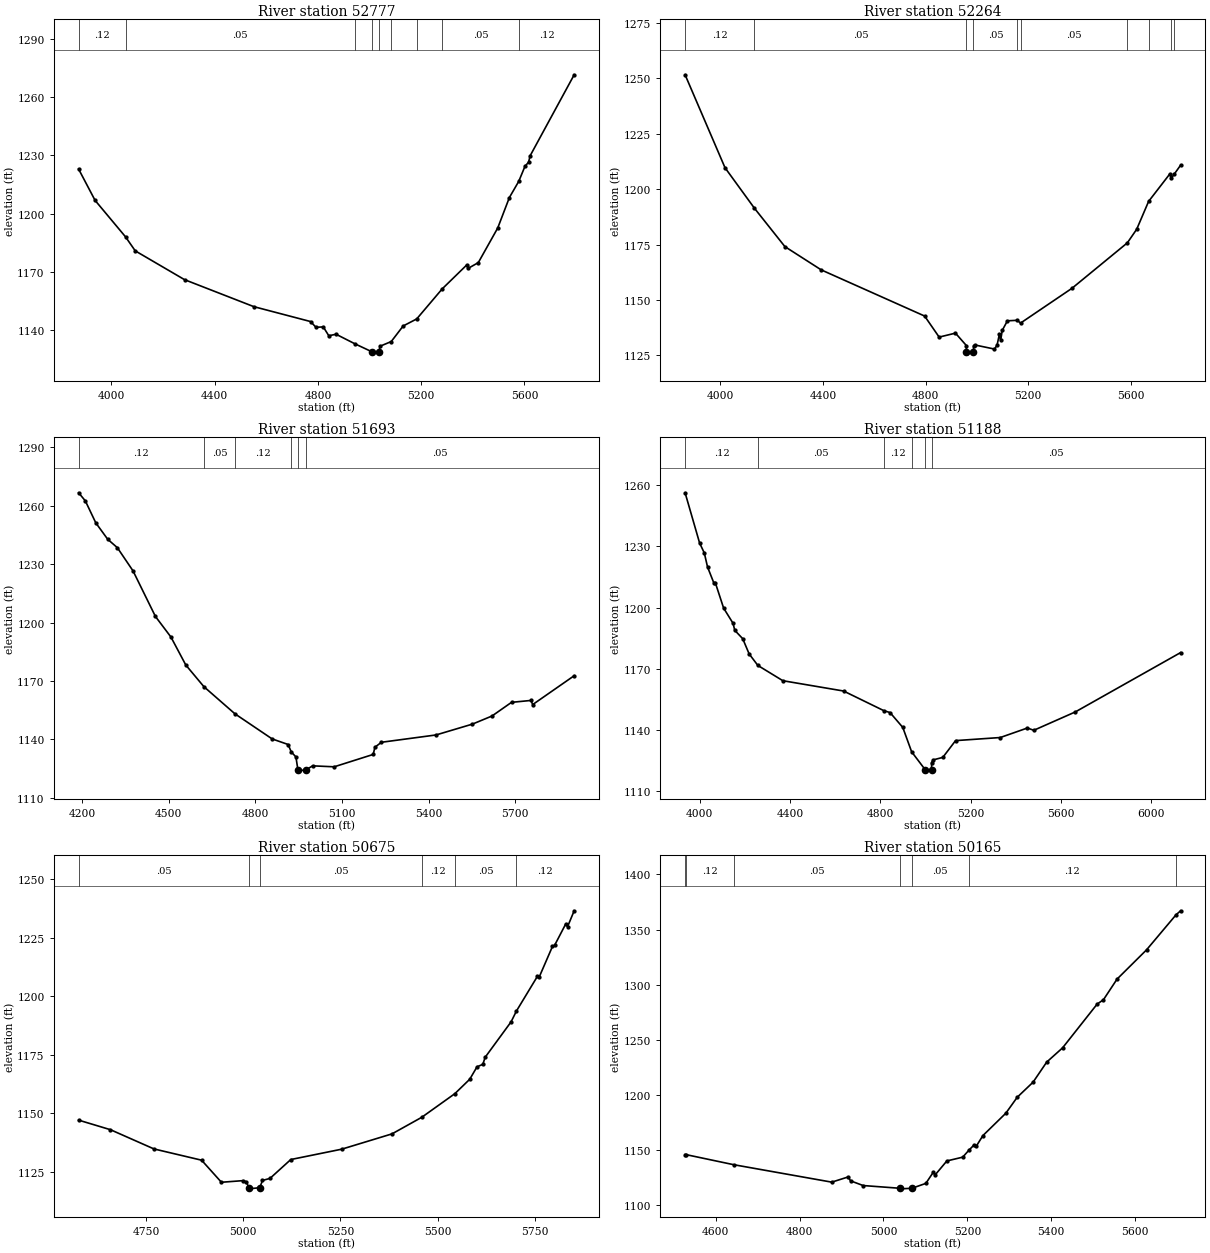
Type RM Length L Ch R = 1 ,52777   ,513,513,513
BEGIN DESCRIPTION:
LITTLE LLANO RIVER 98.0
END DESCRIPTION:
XS GIS Cut Line= 3
      2838205.69     10292553.12       2837395.5       10291770.
      2836605.73     10291703.12
#Sta/Elev= 30
  3873.2 1222.98  3936.9 1206.88  4054.9 1188.09  4092.5 1180.88  4283.4 1166.05
  4552.2 1152.13  4771.4 1144.48  4792.5 1141.52  4820.8 1141.71  4842.1 1137.18
  4870.4 1137.93    4944 1132.97  5009.9 1128.86  5010.4 1128.36  5037.3 1128.86
    5040 1131.73    5084 1134.17  5130.3  1142.2  5182.7 1145.82  5281.5 1161.31
    5377 1173.68    5382 1171.87  5421.3 1174.83  5496.5 1192.66  5541.7 1208.36
  5577.9 1216.68    5602 1224.41    5616 1226.56    5622 1229.85  5792.6 1271.57
#Mann= 9 ,-1 , 0
  3873.2     .12       0  4054.9     .05       0    4944     .12       0
  5009.9     .07       0  5037.3     .12       0    5084     .05       0
  5182.7     .12       0  5281.5     .05       0  5577.9     .12       0
Bank Sta=5009.9,5037.3
XS Rating Curve= 0 ,0
Exp/Cntr=0.3,0.1

Type RM Length L Ch R = 1 ,52264   ,571,571,571
BEGIN DESCRIPTION:
LITTLE LLANO RIVER 97.0
END DESCRIPTION:
XS GIS Cut Line= 3
      2838505.66     10292153.09        2837694.       10291357.
      2836905.64     10291453.12
#Sta/Elev= 30
  3863.1 1251.58  4018.6 1209.65  4133.5 1191.34    4252 1174.06  4393.5 1163.56
  4796.5 1142.73  4853.1 1133.23  4916.7 1135.02  4959.1 1129.43  4959.5 1126.63
    4960 1126.13  4986.9 1126.63  4987.4 1129.31  4994.5 1129.63  5068.8 1127.83
  5078.9 1129.62  5087.9 1134.53  5092.9 1131.78    5099 1136.27  5119.2 1140.58
  5157.8 1140.81  5170.2 1139.54    5371 1155.27  5586.5 1175.75  5622.9 1181.87
  5669.4 1194.46  5750.8 1206.66  5758.4 1205.04  5769.5  1206.8  5794.2 1210.81
#Mann= 10 ,-1 , 0
  3863.1     .12       0  4133.5     .05       0  4959.5     .05       0
  4986.9     .05       0  5157.8     .12       0  5170.2     .05       0
  5586.5     .12       0  5669.4     .05       0  5758.4     .12       0
  5769.5     .05       0
Bank Sta=4959.5,4986.9
XS Rating Curve= 0 ,0
Exp/Cntr=0.3,0.1

Type RM Length L Ch R = 1 ,51693   ,505,505,505
BEGIN DESCRIPTION:
LITTLE LLANO RIVER 96.0
END DESCRIPTION:
XS GIS Cut Line= 3
       2838755.7     10291053.11      2837968.25       10290857.
      2837155.66     10291253.12
#Sta/Elev= 30
  4188.5 1266.72  4211.7 1262.56  4247.9 1251.27  4289.2 1242.83  4322.5 1238.52
  4376.9 1226.57  4454.4 1203.17    4508 1192.62  4559.5 1178.24  4622.2  1167.1
  4729.6 1153.17  4858.4 1140.27  4913.8  1137.4  4924.4 1133.63  4940.8    1131
  4947.6 1124.37  4948.1 1123.87  4975.2 1124.37  4998.7 1126.44  5073.1 1125.94
  5208.3  1132.3  5214.2 1135.98  5236.5 1138.54  5425.6  1142.3  5551.9 1147.88
  5619.5 1152.04  5687.1 1159.06  5754.7 1160.04  5760.3  1157.9    5904 1172.73
#Mann= 6 ,-1 , 0
  4188.5     .12       0  4622.2     .05       0  4729.6     .12       0
  4924.4     .05       0  4947.6     .03       0  4975.2     .05       0
Bank Sta=4947.6,4975.2
XS Rating Curve= 0 ,0
Exp/Cntr=0.3,0.1

Type RM Length L Ch R = 1 ,51188   ,513,513,513
BEGIN DESCRIPTION:
LITTLE LLANO RIVER 95.0
END DESCRIPTION:
XS GIS Cut Line= 3
      2838655.71     10289703.09      2837846.75       10290395.
      2837055.65     10291203.14
#Sta/Elev= 30
  3935.5 1256.14  3999.8 1231.55  4020.6 1226.69  4034.9 1219.84  4063.4 1211.85
    4070 1211.93  4106.2  1199.7  4147.9 1192.27  4155.6 1188.83  4190.8 1184.74
  4219.3 1177.28  4257.9 1171.65  4368.6 1164.18  4637.5 1159.14  4814.8 1149.59
  4843.5 1148.59  4899.9 1141.33  4939.1  1129.4  4999.6 1120.58  5000.1 1120.08
  5027.4 1120.58  5027.7 1124.15  5034.8 1125.45  5077.2 1126.66  5133.8 1134.87
  5331.8 1136.38    5452 1141.04  5480.3 1139.92  5664.2  1148.9  6130.9 1177.95
#Mann= 6 ,-1 , 0
  3935.5     .12       0  4257.9     .05       0  4814.8     .12       0
  4939.1     .05       0  4999.6     .03       0  5027.4     .05       0
Bank Sta=4999.6,5027.4
XS Rating Curve= 0 ,0
Exp/Cntr=0.3,0.1

Type RM Length L Ch R = 1 ,50675   ,510,510,510
BEGIN DESCRIPTION:
LITTLE LLANO RIVER 94.0
END DESCRIPTION:
XS GIS Cut Line= 3
      2837505.68     10289703.11      2837423.25       10290118.
      2836605.68     10290353.11
#Sta/Elev= 30
    4577 1147.15  4658.8 1143.06  4770.7 1134.84  4893.1 1130.03    4944  1120.6
    5000  1121.3  5007.9  1120.8  5014.7 1118.29  5015.2 1117.79  5042.6 1118.29
  5049.5 1121.37  5068.9 1122.26  5122.3 1130.31    5253 1134.73  5382.5 1141.28
  5458.9 1148.36    5544 1158.46  5582.3 1164.63    5601 1169.94    5616 1171.01
  5621.8 1173.99  5688.6 1189.17  5702.2 1193.75    5756 1208.54  5761.2 1208.44
  5794.9 1221.37  5800.2 1221.79  5828.6 1230.86  5833.9 1229.89  5850.7 1236.62
#Mann= 6 ,-1 , 0
    4577     .05       0  5014.7     .05       0  5042.6     .05       0
  5458.9     .12       0    5544     .05       0  5702.2     .12       0
Bank Sta=5014.7,5042.6
XS Rating Curve= 0 ,0
Exp/Cntr=0.3,0.1

Type RM Length L Ch R = 1 ,50165   ,508,508,508
BEGIN DESCRIPTION:
LITTLE LLANO RIVER 93.0
END DESCRIPTION:
XS GIS Cut Line= 3
      2837405.64     10289653.13      2836982.25       10289864.
      2836305.66      10289653.1
#Sta/Elev= 30
    4527 1145.52  4530.2 1145.45    4643 1136.37  4876.7 1120.53  4915.9 1125.26
  4921.5 1121.73  4951.5 1117.45  5039.7 1114.95  5040.2 1114.45  5067.7 1114.95
  5101.1  1119.4  5118.7 1129.45    5124 1127.44  5151.2 1139.79    5189 1143.23
  5203.4 1149.37  5216.3 1154.42  5221.5 1153.29  5237.3 1162.87  5291.8 1183.12
  5319.1 1197.66  5356.8 1211.33  5389.3 1229.57  5427.1 1242.48  5509.7 1282.31
  5524.6  1286.2  5557.1 1304.97  5627.4 1331.52  5697.8 1363.39  5708.7 1367.01
#Mann= 7 ,-1 , 0
    4527     .05       0  4530.2     .12       0    4643     .05       0
  5039.7     .05       0  5067.7     .05       0  5203.4     .12       0
  5697.8     .05       0
Bank Sta=5039.7,5067.7
XS Rating Curve= 0 ,0
Exp/Cntr=0.3,0.1

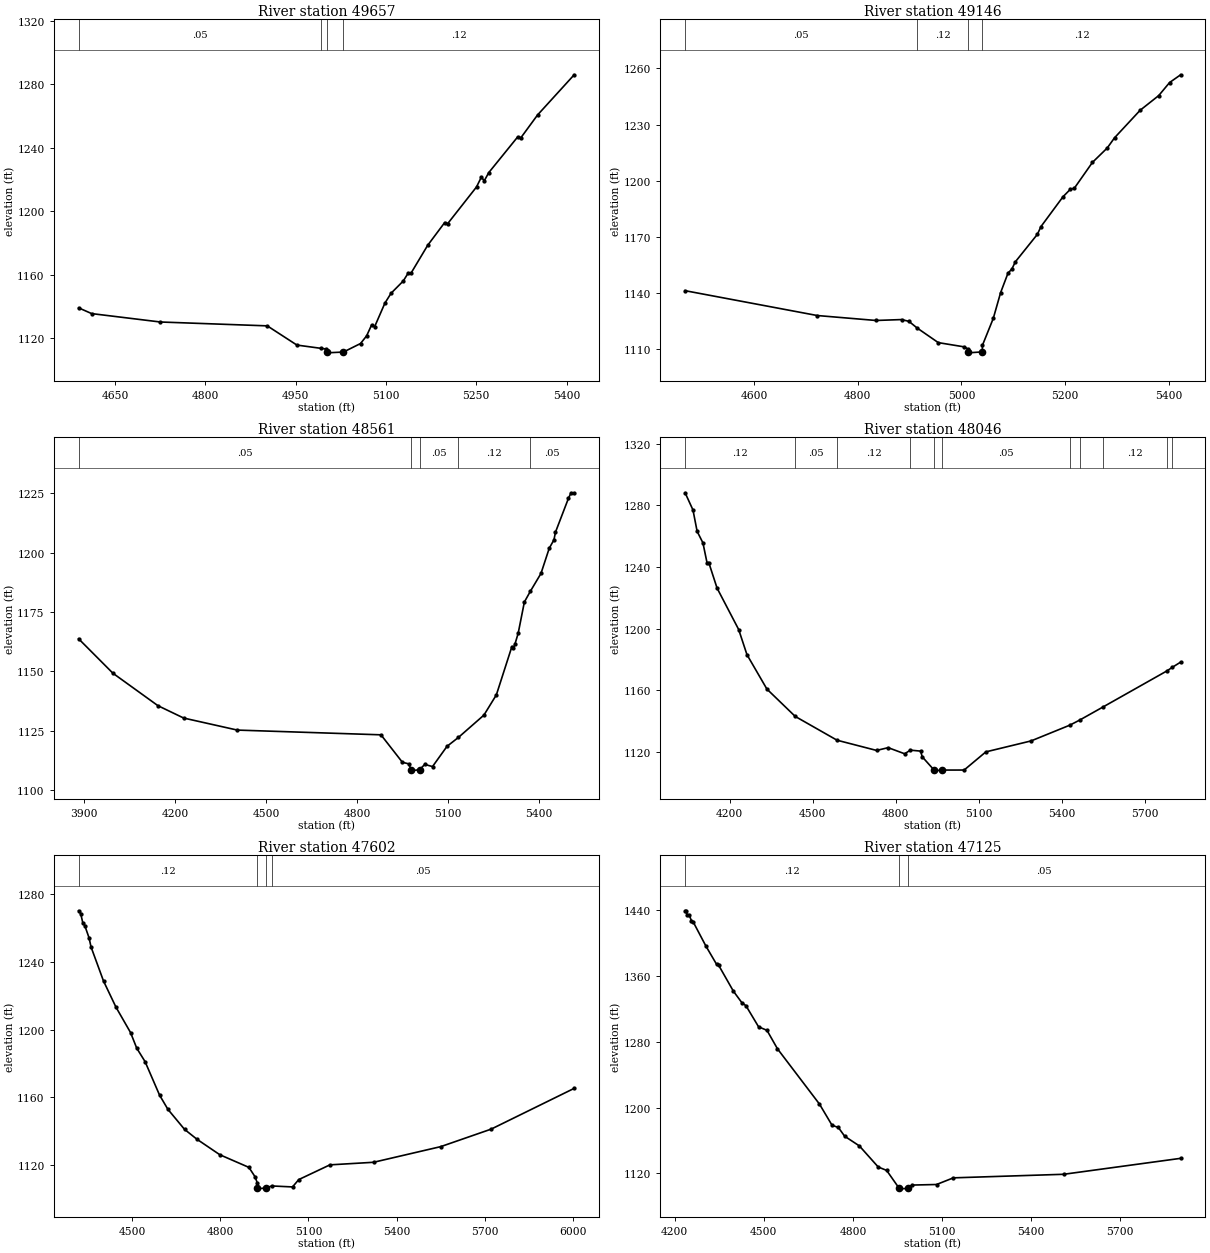
Type RM Length L Ch R = 1 ,49657   ,511,511,511
BEGIN DESCRIPTION:
LITTLE LLANO RIVER 92.0
END DESCRIPTION:
XS GIS Cut Line= 3
      2837305.68     10289503.11      2836912.75       10289385.
      2836505.71     10289453.11
#Sta/Elev= 30
  4589.7 1139.22  4611.4  1135.6  4725.4 1130.32    4903 1127.89  4952.2  1115.8
    4992 1113.75    5000 1113.35  5001.5 1111.41    5002 1110.91  5029.5 1111.41
  5057.9 1116.78    5068  1121.6  5076.3 1128.48  5081.3 1127.35  5098.4 1142.22
  5108.6 1148.41  5128.8 1156.11    5137 1161.09    5142 1161.22  5169.4 1178.58
  5197.7 1192.93  5202.8 1192.31  5250.5 1215.31  5258.4 1221.37  5263.5 1219.27
  5270.8 1224.31  5319.1  1246.9  5324.2 1246.29  5351.9 1260.62  5412.7 1285.91
#Mann= 4 ,-1 , 0
  4589.7     .05       0    4992     .12       0  5001.5     .07       0
  5029.5     .12       0
Bank Sta=5001.5,5029.5
XS Rating Curve= 0 ,0
Exp/Cntr=0.3,0.1

Type RM Length L Ch R = 1 ,49146   ,585,585,585
BEGIN DESCRIPTION:
LITTLE LLANO RIVER 91.0
END DESCRIPTION:
XS GIS Cut Line= 3
      2837455.69     10289303.12      2837089.75       10288916.
      2836805.69     10288603.11
#Sta/Elev= 30
  4467.3 1141.36    4722 1128.11  4835.2 1125.47  4884.6 1125.95  4898.8    1125
  4914.5 1121.47  4955.4 1113.65  5005.3 1111.39  5012.1 1110.36  5012.3  1108.7
  5012.8  1108.2  5040.3  1108.7  5040.5 1112.21  5061.4 1126.57  5075.6 1140.36
  5089.8 1150.73  5097.2 1152.89    5104 1156.78  5146.5 1171.46  5153.3 1175.55
  5195.9 1191.51  5210.1  1195.5  5217.5 1195.97  5252.6 1209.82    5281 1217.47
  5295.2 1222.94  5344.5 1237.62  5380.4 1245.47  5401.3 1252.42  5422.6 1256.56
#Mann= 4 ,-1 , 0
  4467.3     .05       0  4914.5     .12       0  5012.3     .07       0
  5040.3     .12       0
Bank Sta=5012.3,5040.3
XS Rating Curve= 0 ,0
Exp/Cntr=0.3,0.1

Type RM Length L Ch R = 1 ,48561   ,515,515,515
BEGIN DESCRIPTION:
LITTLE LLANO RIVER 90.0
END DESCRIPTION:
XS GIS Cut Line= 3
       2838355.7     10289353.12       2837558.5       10288569.
      2837055.68     10288453.11
#Sta/Elev= 30
  3881.8 1163.72  3994.9 1149.24  4143.5 1135.58  4228.3 1130.39  4405.1 1125.33
  4878.8 1123.34  4949.5 1111.79  4970.8 1111.12  4977.9 1108.69  4978.4 1108.19
    5006 1108.69  5023.4  1110.9  5048.8 1109.98  5096.7  1118.5  5134.2 1122.23
  5218.4 1131.63  5259.4 1140.14  5310.6 1160.44  5315.8 1159.68    5321 1161.62
  5331.3 1166.02  5351.8 1179.21  5371.3 1183.66  5406.5  1191.2  5433.9 1201.84
  5449.3 1205.34  5454.4 1208.59  5497.2 1222.83  5505.7 1225.14    5516 1224.86
#Mann= 5 ,-1 , 0
  3881.8     .05       0  4977.9     .03       0    5006     .05       0
  5134.2     .12       0  5371.3     .05       0
Bank Sta=4977.9,5006
XS Rating Curve= 0 ,0
Exp/Cntr=0.3,0.1

Type RM Length L Ch R = 1 ,48046   ,444,444,444
BEGIN DESCRIPTION:
LITTLE LLANO RIVER 89.0
END DESCRIPTION:
XS GIS Cut Line= 3
      2838805.66     10288853.09       2838006.5       10288319.
      2837355.67      10287803.1
#Sta/Elev= 30
  4038.8 1288.22  4067.3 1277.03  4082.3 1263.15  4103.3 1255.65  4118.3 1242.56
  4124.4 1242.87  4154.4 1226.26  4232.5 1199.37  4262.5 1183.01  4334.6 1160.66
  4437.1 1142.88  4588.2 1127.43    4731 1120.79  4773.1 1122.59  4832.6 1118.62
  4853.3 1120.97  4890.2 1120.35  4896.2 1116.65  4939.1 1108.03  4939.6 1107.53
  4967.3 1108.03  5047.7 1108.05  5126.2 1119.85  5289.7 1126.97  5430.1 1137.23
  5465.9 1140.56  5549.8 1149.02    5781 1172.47  5799.5 1174.71  5830.5 1178.18
#Mann= 11 ,-1 , 0
  4038.8     .12       0  4437.1     .05       0  4588.2     .12       0
  4853.3     .05       0  4939.1     .03       0  4967.3     .05       0
  5430.1     .12       0  5465.9     .05       0  5549.8     .12       0
    5781     .05       0  5799.5     .12       0
Bank Sta=4939.1,4967.3
XS Rating Curve= 0 ,0
Exp/Cntr=0.3,0.1

Type RM Length L Ch R = 1 ,47602   ,477,477,477
BEGIN DESCRIPTION:
LITTLE LLANO RIVER 88.0
END DESCRIPTION:
XS GIS Cut Line= 3
      2838879.67     10288598.97       2838158.3     10287869.98
      2837543.73     10287625.19
#Sta/Elev= 30
  4317.7 1270.21  4324.7 1268.55  4331.7 1263.24  4338.8 1261.35    4353 1254.31
    4360 1248.79  4402.4 1228.68  4444.9 1213.19  4494.4 1198.22  4515.6 1188.94
  4543.9 1181.02  4593.3 1161.18  4621.6 1152.82  4678.2 1140.98  4720.6 1135.11
  4798.4 1125.96  4897.4 1118.49  4918.6 1112.86  4925.7 1109.36  4925.8  1106.3
  4926.3  1105.8    4954  1106.3  4975.9  1107.5  5045.9 1106.93  5067.1 1111.27
  5173.2 1119.98  5321.7  1121.5  5550.6 1130.76  5722.1  1141.1  6004.8 1165.21
#Mann= 4 ,-1 , 0
  4317.7     .12       0  4925.8     .05       0    4954     .12       0
  4975.9     .05       0
Bank Sta=4925.8,4954
XS Rating Curve= 0 ,0
Exp/Cntr=0.3,0.1

Type RM Length L Ch R = 1 ,47125   ,516,516,516
BEGIN DESCRIPTION:
LITTLE LLANO RIVER 87.0
END DESCRIPTION:
XS GIS Cut Line= 3
      2839355.65     10288403.08       2838808.5       10287868.
      2838005.67      10287453.1
#Sta/Elev= 30
  4234.7 1439.31  4238.2 1439.31  4241.7 1434.21  4248.7 1434.14  4255.9 1427.21
  4262.9 1425.12  4305.3 1396.06  4340.7 1374.25  4347.7 1373.07  4397.3 1341.59
  4425.6 1327.71  4439.8 1323.82  4482.2 1298.23  4510.5 1293.96  4545.8 1271.49
  4687.2 1204.33  4729.6 1178.58  4750.9 1175.85  4772.1 1165.23  4821.7 1153.43
  4885.2 1127.79  4913.5 1123.67    4956 1101.75  4956.5 1101.25  4984.2 1101.75
  4998.4 1105.83  5081.6 1106.52  5138.2 1114.61  5509.7 1118.94  5903.7 1138.33
#Mann= 3 ,-1 , 0
  4234.7     .12       0    4956     .05       0  4984.2     .05       0
Bank Sta=4956,4984.2
XS Rating Curve= 0 ,0
Exp/Cntr=0.3,0.1

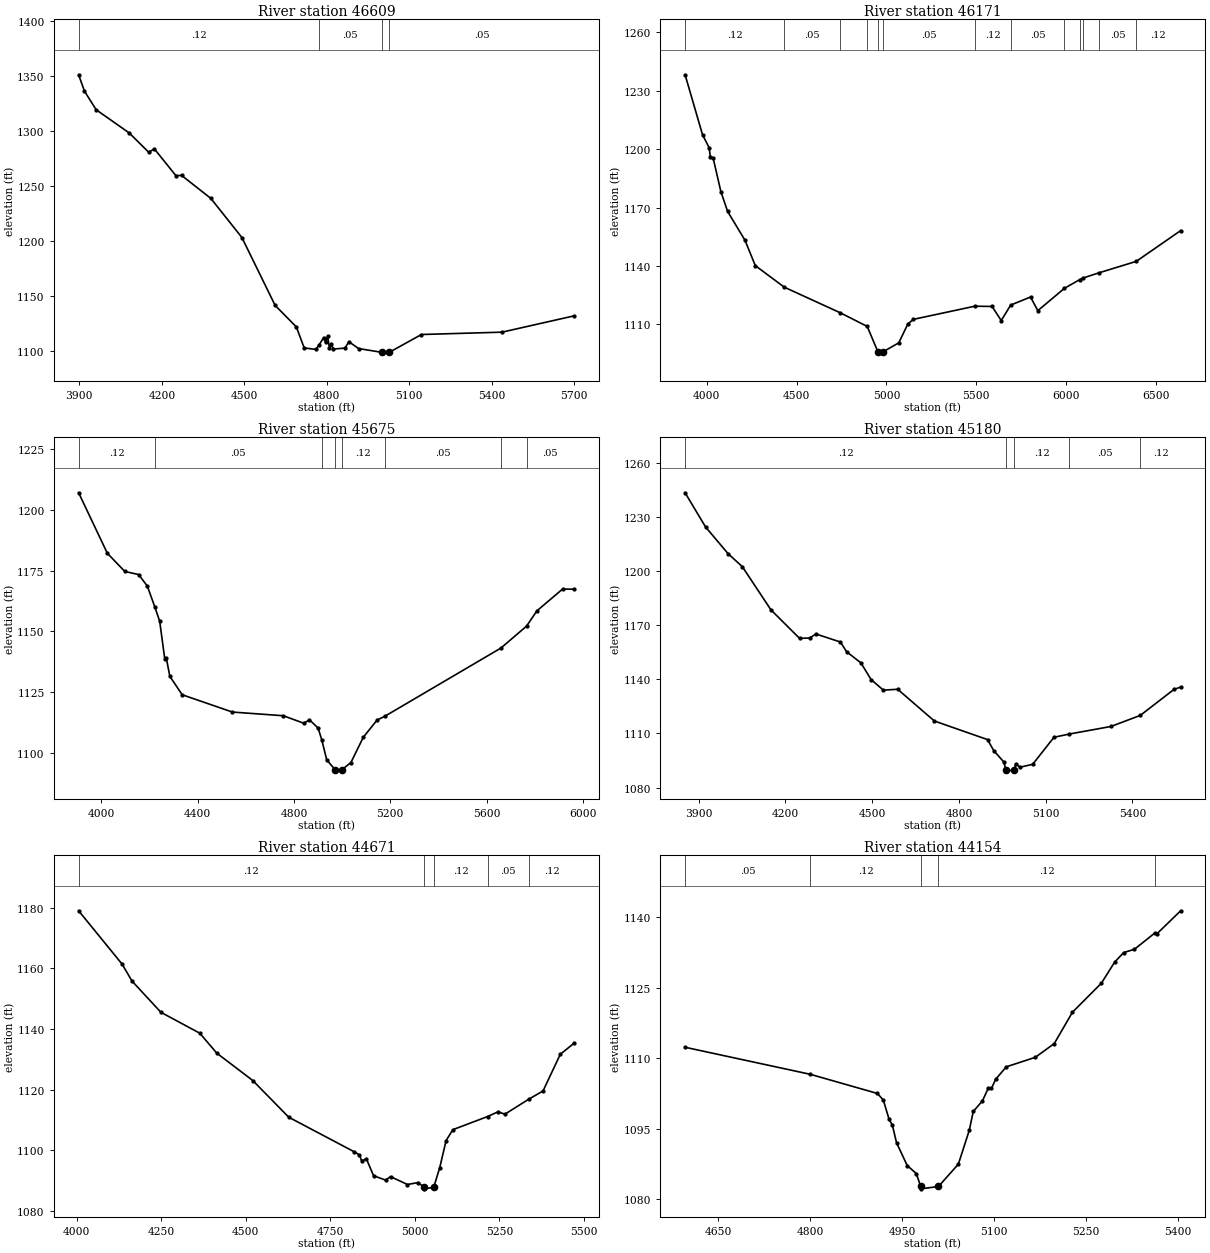
Type RM Length L Ch R = 1 ,46609   ,438,438,438
BEGIN DESCRIPTION:
LITTLE LLANO RIVER 86.0
END DESCRIPTION:
XS GIS Cut Line= 3
      2839655.68     10288253.11        2838899.       10287451.
      2838205.68     10287353.11
#Sta/Elev= 30
  3897.3 1351.36  3918.5 1336.46    3961 1319.52  4081.2 1298.38    4152 1280.84
    4173 1283.79  4251.1 1259.48  4272.1 1259.64  4378.5 1238.66  4491.4 1203.04
    4612 1141.32  4689.6 1121.54    4718 1102.44  4760.4 1101.13  4771.5 1104.89
  4788.8 1111.96  4795.6 1107.48  4802.9    1113  4809.8 1102.71  4817.1 1105.73
    4824 1101.44  4866.4 1102.31  4880.6 1108.14  4915.8 1101.91  4999.3  1098.5
  4999.8    1098  5027.6  1098.5  5144.7 1114.71  5437.6 1116.84  5700.2 1131.71
#Mann= 4 ,-1 , 0
  3897.3     .12       0  4771.5     .05       0  4999.3     .05       0
  5027.6     .05       0
Bank Sta=4999.3,5027.6
XS Rating Curve= 0 ,0
Exp/Cntr=0.3,0.1

Type RM Length L Ch R = 1 ,46171   ,496,496,496
BEGIN DESCRIPTION:
LITTLE LLANO RIVER 85.0
END DESCRIPTION:
XS GIS Cut Line= 3
      2839705.22     10287515.84      2839028.09      10287130.4
       2837085.4      10286755.4
#Sta/Elev= 30
  3879.2 1238.17  3976.1 1207.42  4013.5  1200.6  4019.3 1196.15  4035.2 1195.46
  4078.4 1178.15  4115.9 1167.98  4212.4 1153.21  4269.9 1140.19    4431 1129.12
  4743.5 1115.93  4892.9 1108.96  4952.2  1095.9  4952.7  1095.4  4980.5  1095.9
  5068.2 1100.53  5119.1 1110.25    5150  1112.6  5491.6 1119.35  5587.6 1119.21
  5638.5 1111.99  5691.1 1119.92  5801.5 1124.06  5842.2 1117.06  5990.5 1128.55
  6074.5 1132.94  6091.2 1133.74  6183.6 1136.52  6389.6 1142.35  6636.9 1158.16
#Mann= 13 ,-1 , 0
  3879.2     .12       0    4431     .05       0  4743.5     .12       0
  4892.9     .05       0  4952.2     .03       0  4980.5     .05       0
  5491.6     .12       0  5691.1     .05       0  5990.5     .12       0
  6074.5     .05       0  6091.2     .12       0  6183.6     .05       0
  6389.6     .12       0
Bank Sta=4952.2,4980.5
XS Rating Curve= 0 ,0
Exp/Cntr=0.3,0.1

Type RM Length L Ch R = 1 ,45675   ,495,495,495
BEGIN DESCRIPTION:
LITTLE LLANO RIVER 84.0
END DESCRIPTION:
XS GIS Cut Line= 3
      2839689.53     10287213.72      2838439.55     10286401.23
      2838013.51     10286027.14
#Sta/Elev= 30
  3905.9 1207.04    4025 1182.16  4097.5 1174.67  4154.9 1173.39  4191.1 1168.64
  4221.8 1160.21  4242.5 1154.17  4263.6 1138.65  4269.5 1139.25  4284.7 1131.48
    4336 1123.92  4544.3  1116.8  4755.8 1115.29  4840.8  1112.2  4864.5 1113.61
  4900.4 1110.21  4915.6 1105.35  4936.2  1097.1  4970.7 1093.11  4971.2 1092.61
  4999.5 1093.11  5036.5    1096  5087.9  1106.4  5145.2 1113.51  5176.1 1114.99
  5659.5 1143.14  5765.8 1152.15  5809.2 1158.48  5915.5  1167.4  5963.7 1167.38
#Mann= 8 ,-1 , 0
  3905.9     .12       0  4221.8     .05       0  4915.6     .12       0
  4970.7     .07       0  4999.5     .12       0  5176.1     .05       0
  5659.5     .12       0  5765.8     .05       0
Bank Sta=4970.7,4999.5
XS Rating Curve= 0 ,0
Exp/Cntr=0.3,0.1

Type RM Length L Ch R = 1 ,45180   ,509,509,509
BEGIN DESCRIPTION:
LITTLE LLANO RIVER 83.0
END DESCRIPTION:
XS GIS Cut Line= 3
      2839905.67      10287053.1      2839093.25       10286243.
      2838605.71     10285953.13
#Sta/Elev= 30
  3852.7 1243.36  3923.4 1224.44  4001.2 1209.66  4050.7 1202.41  4149.7 1178.48
  4248.7  1162.7    4284 1162.88  4305.2 1165.13  4390.1 1160.66  4411.3  1155.3
  4460.8 1149.14  4496.2 1139.86  4538.6 1133.99  4588.1 1134.49  4715.3 1116.88
  4899.2 1106.59  4920.4 1100.52  4955.8 1094.11  4962.5 1089.78    4963 1089.28
  4991.4 1089.78  4996.4 1093.09  5012.1 1091.32  5055.3 1092.89    5129 1107.88
  5181.9 1109.67  5325.7 1113.85  5427.5 1119.99    5544 1134.38  5567.2  1135.7
#Mann= 5 ,-1 , 0
  3852.7     .12       0  4962.5     .07       0  4991.4     .12       0
  5181.9     .05       0  5427.5     .12       0
Bank Sta=4962.5,4991.4
XS Rating Curve= 0 ,0
Exp/Cntr=0.3,0.1

Type RM Length L Ch R = 1 ,44671   ,517,517,517
BEGIN DESCRIPTION:
LITTLE LLANO RIVER 82.0
END DESCRIPTION:
XS GIS Cut Line= 3
      2839755.69     10286553.12      2839166.25       10285753.
      2838705.66     10285653.11
#Sta/Elev= 30
  4006.2 1179.04  4134.6 1161.44  4163.9 1155.84  4249.5 1145.51  4364.5  1138.6
  4414.6 1132.03  4521.1 1122.98  4627.5 1110.86  4821.8  1099.4  4836.5 1098.41
  4842.7 1096.51  4857.3 1097.03  4878.2 1091.54  4913.7  1090.1  4928.3 1091.25
  4978.4 1088.64  5010.8  1089.3  5027.1 1087.71  5027.6 1087.21    5056 1087.71
  5073.8  1094.2  5092.7 1103.17  5112.7 1106.75  5215.1 1111.08  5246.2 1112.65
  5266.6 1111.87  5337.1 1116.82  5379.2 1119.53  5430.3 1131.65  5471.3 1135.33
#Mann= 5 ,-1 , 0
  4006.2     .12       0  5027.1     .07       0    5056     .12       0
  5215.1     .05       0  5337.1     .12       0
Bank Sta=5027.1,5056
XS Rating Curve= 0 ,0
Exp/Cntr=0.3,0.1

Type RM Length L Ch R = 1 ,44154   ,507,507,507
BEGIN DESCRIPTION:
LITTLE LLANO RIVER 81.0
END DESCRIPTION:
XS GIS Cut Line= 3
      2839655.71     10285403.12      2839280.75       10285253.
      2838905.69     10285103.11
#Sta/Elev= 30
  4596.1 1112.35  4800.1  1106.6  4909.7 1102.52  4919.3  1101.1  4928.6 1097.03
  4933.9 1095.82  4940.8 1092.04  4958.2 1087.18  4973.1 1085.48  4980.1 1082.73
  4980.6 1082.23  5009.1 1082.73  5041.6 1087.49  5059.3 1094.67  5065.9  1098.7
  5080.8 1100.94  5090.1 1103.59  5095.5 1103.59  5102.4 1105.55  5119.7 1108.19
    5167 1110.21  5197.9 1113.14  5227.5  1119.8  5274.7 1125.98  5296.2 1130.44
    5311  1132.5  5328.5 1133.19    5362 1136.68  5364.9 1136.45  5403.9 1141.39
#Mann= 5 ,-1 , 0
  4596.1     .05       0  4800.1     .12       0  4980.1     .07       0
  5009.1     .12       0    5362     .05       0
Bank Sta=4980.1,5009.1
XS Rating Curve= 0 ,0
Exp/Cntr=0.3,0.1

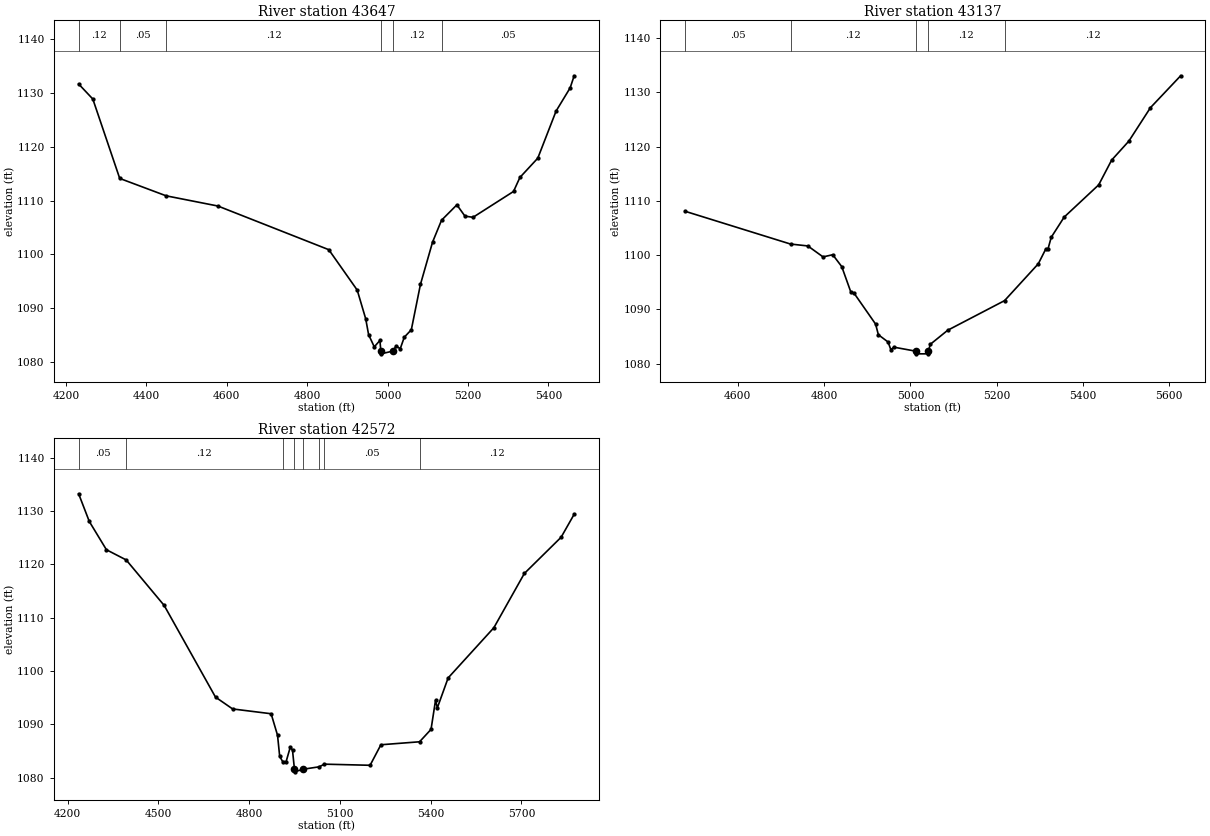
Type RM Length L Ch R = 1 ,43647   ,510,510,510
BEGIN DESCRIPTION:
LITTLE LLANO RIVER 80.0
END DESCRIPTION:
XS GIS Cut Line= 3
      2840055.68      10285353.1        2839517.       10284805.
      2839055.71     10284753.11
#Sta/Elev= 30
  4231.5 1131.71  4266.8 1128.91  4333.7 1114.13  4449.2 1110.89    4578 1108.99
  4853.8 1100.86  4924.5 1093.34  4945.7 1087.97  4952.8 1085.05  4966.9 1082.77
    4981 1083.96  4983.3 1081.97  4983.8 1081.47  5012.4 1081.97  5021.5 1082.92
  5031.5 1082.42  5041.6 1084.57  5059.1 1085.95  5081.8  1094.4    5112 1102.29
  5134.3 1106.35  5172.4 1109.21  5192.5 1107.11  5212.6 1106.89  5313.3  1111.7
  5329.2 1114.31  5373.7  1117.9  5419.2 1126.67  5454.2 1130.99  5464.2 1133.24
#Mann= 6 ,-1 , 0
  4231.5     .12       0  4333.7     .05       0  4449.2     .12       0
  4983.3     .07       0  5012.4     .12       0  5134.3     .05       0
Bank Sta=4983.3,5012.4
XS Rating Curve= 0 ,0
Exp/Cntr=0.3,0.1

Type RM Length L Ch R = 1 ,43137   ,565,565,565
BEGIN DESCRIPTION:
LITTLE LLANO RIVER 79.0
END DESCRIPTION:
XS GIS Cut Line= 3
      2840055.68     10284753.11      2839732.25       10284343.
      2839105.73     10284353.11
#Sta/Elev= 30
  4477.7 1108.09  4722.1 1102.05  4762.3  1101.7  4797.5 1099.68    4820 1100.08
  4840.9 1097.89  4861.7 1093.26  4869.7 1092.96  4919.4 1087.29  4925.8 1085.33
  4948.3 1083.99  4954.7 1082.58  4961.7 1083.04  5011.9 1082.31  5012.4 1081.81
  5040.8 1081.81  5041.3 1082.31  5046.6 1083.59  5086.6 1086.16  5218.4 1091.62
  5296.6 1098.41  5314.2 1101.18  5319.2 1101.18  5326.6  1103.3  5356.6 1107.02
  5436.6 1112.96  5466.6 1117.52  5506.6 1121.03  5556.6 1127.19  5626.6 1133.07
#Mann= 5 ,-1 , 0
  4477.7     .05       0  4722.1     .12       0  5011.9     .07       0
  5041.3     .12       0  5218.4     .12       0
Bank Sta=5011.9,5041.3
XS Rating Curve= 0 ,0
Exp/Cntr=0.3,0.1

Type RM Length L Ch R = 1 ,42572   ,377,377,377
BEGIN DESCRIPTION:
LITTLE LLANO RIVER 78.0
END DESCRIPTION:
XS GIS Cut Line= 3
      2840405.68     10283253.12      2839867.25       10283795.
      2839155.65     10284303.14
#Sta/Elev= 30
  4236.1 1133.26  4271.4 1128.06    4328 1122.76  4393.3 1120.85  4518.9 1112.31
  4688.6 1095.11  4745.2 1092.89  4872.5 1091.99  4893.7 1087.95  4900.8 1083.99
  4910.6 1083.02    4922 1082.99  4936.1 1085.78  4943.2 1085.13  4949.6 1081.59
  4950.1 1081.09  4979.3 1081.59  5031.1 1082.03  5048.8 1082.53  5199.7 1082.32
  5235.4 1086.17  5363.3 1086.73  5401.2 1089.06    5416  1094.5  5422.1 1093.11
  5457.7 1098.71  5608.9 1108.13  5709.7 1118.31  5831.3 1125.11  5874.4 1129.42
#Mann= 8 ,-1 , 0
  4236.1     .05       0  4393.3     .12       0  4910.6     .05       0
  4949.6     .03       0  4979.3     .05       0  5031.1     .12       0
  5048.8     .05       0  5363.3     .12       0
Bank Sta=4949.6,4979.3
XS Rating Curve= 0 ,0
Exp/Cntr=0.3,0.1