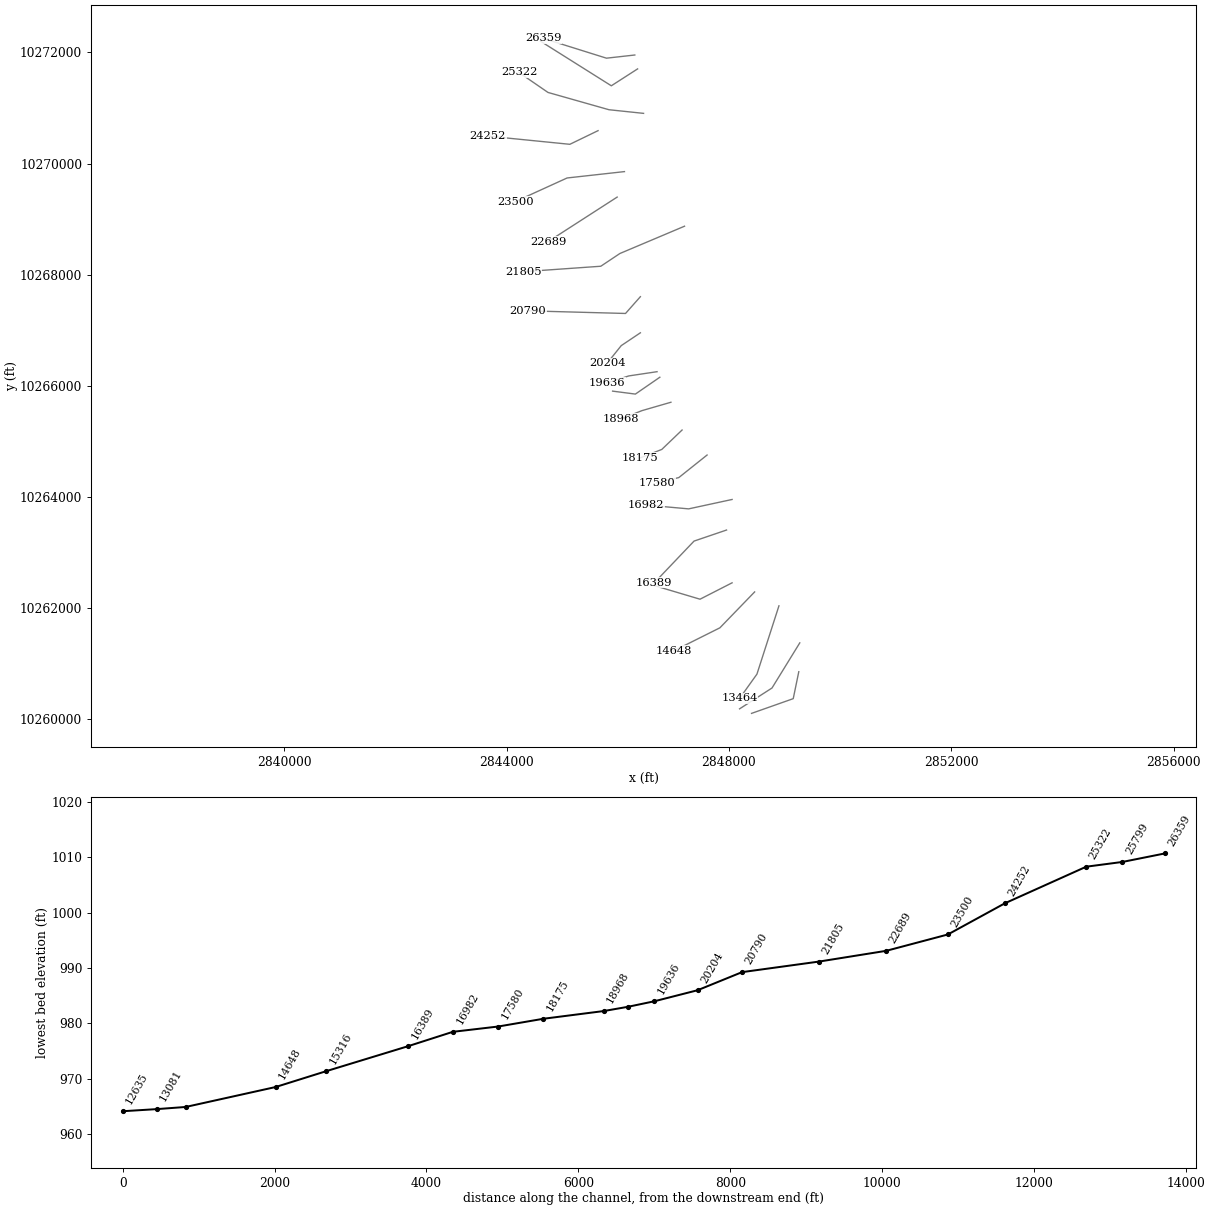
HEC-RAS study LITTLE LLANO RIVER.prj: LITTLE LLANO RIVER Base Level Engineering

--- LITTLE LLANO RIVER.g01 (geometry) --- (continued)

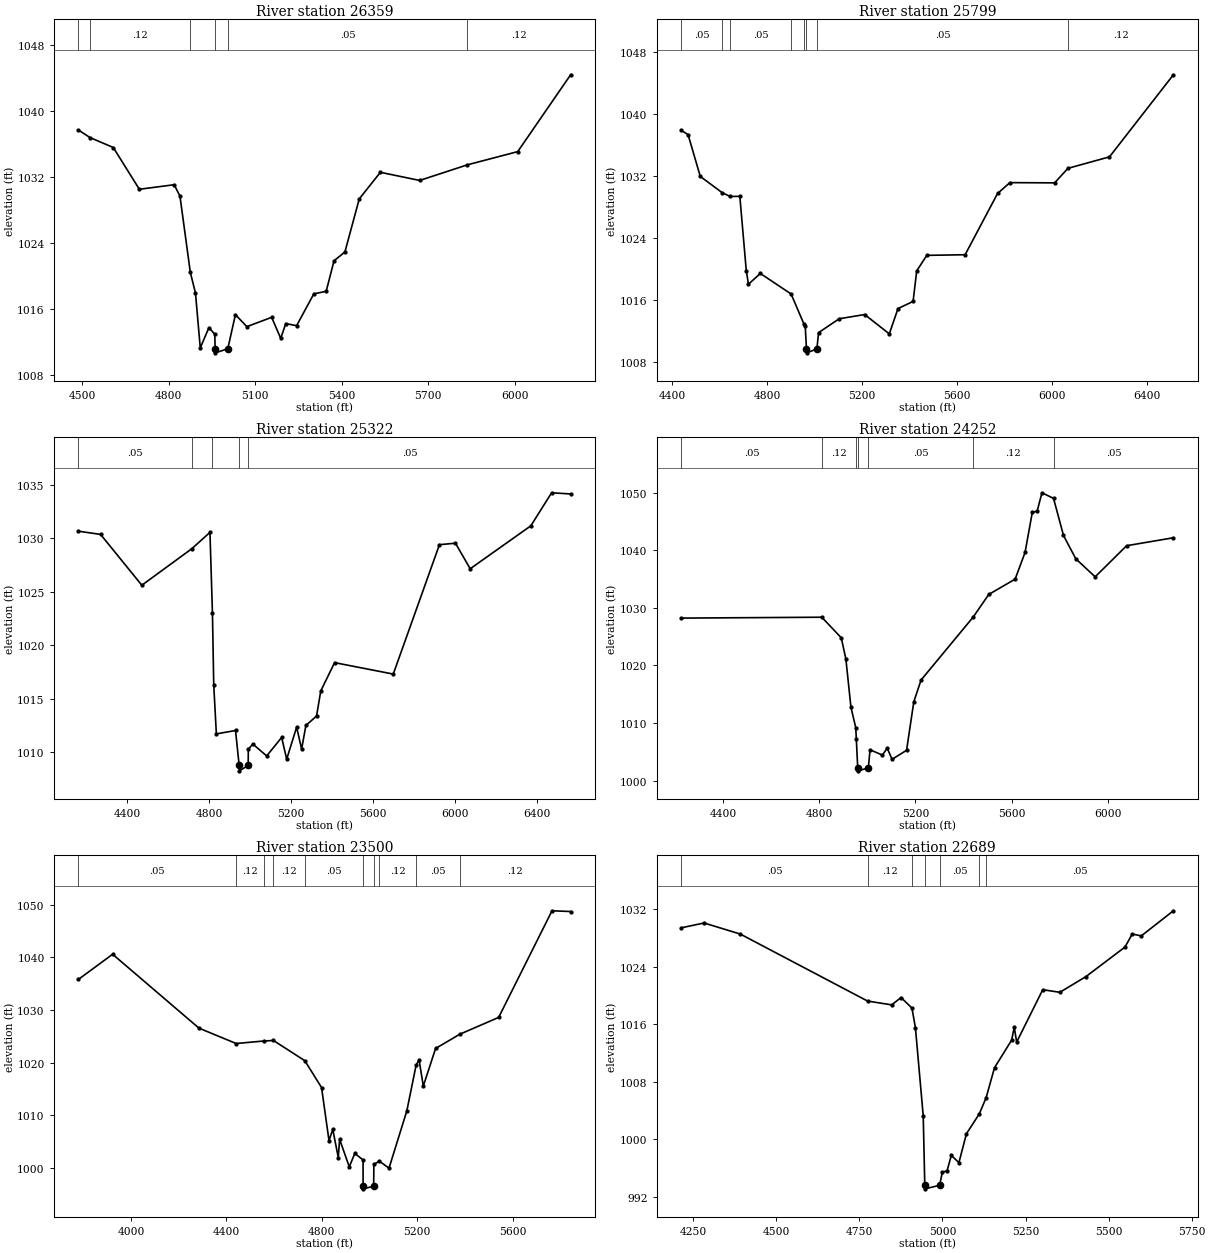
Type RM Length L Ch R = 1 ,26359   ,560,560,560
BEGIN DESCRIPTION:
LITTLE LLANO RIVER 46.0
END DESCRIPTION:
XS GIS Cut Line= 3
      2846305.71     10271953.11       2845795.5       10271896.
      2844655.73      10272253.1
#Sta/Elev= 30
  4486.6 1037.73  4526.5 1036.82  4607.4 1035.61  4697.9 1030.54  4818.7 1031.09
  4838.8 1029.71  4874.8 1020.44  4892.6 1017.94  4909.3 1011.28  4939.4 1013.75
  4959.6 1012.93  4960.9 1011.18  4961.9 1010.68  5004.8 1011.18  5031.2 1015.32
  5070.9 1013.86    5157 1014.99  5188.4 1012.44    5206 1014.23  5243.6 1013.98
  5303.3 1017.84  5346.2 1018.15  5373.4 1021.86  5411.1 1022.92  5460.9 1029.37
  5534.3  1032.6  5670.5 1031.61  5836.4 1033.51  6010.8 1035.11  6194.4 1044.44
#Mann= 6 ,-1 , 0
  4486.6     .05       0  4526.5     .12       0  4874.8     .05       0
  4960.9     .05       0  5004.8     .05       0  5836.4     .12       0
Bank Sta=4960.9,5004.8
XS Rating Curve= 0 ,0
Exp/Cntr=0.3,0.1

Type RM Length L Ch R = 1 ,25799   ,477,477,477
BEGIN DESCRIPTION:
LITTLE LLANO RIVER 45.0
END DESCRIPTION:
XS GIS Cut Line= 3
      2846355.72     10271703.13        2845883.       10271399.
      2844605.72     10272203.09
#Sta/Elev= 30
  4437.9 1037.89  4466.7 1037.35  4518.2 1031.94  4609.5 1029.86  4643.7 1029.35
  4684.6 1029.37  4711.7 1019.77  4720.9 1018.01  4770.9  1019.4  4900.3 1016.75
  4953.7 1012.91  4959.9 1012.57  4965.1 1009.64  4966.1 1009.14    5009 1009.64
  5015.8 1011.75  5103.2 1013.55  5210.1 1014.09  5313.7 1011.59  5350.2 1014.86
  5413.8 1015.79  5429.1 1019.74  5471.5 1021.74  5632.8 1021.82  5769.4 1029.74
  5821.2 1031.14  6009.5 1031.11  6065.6 1032.99  6240.3 1034.47  6509.3 1045.08
#Mann= 8 ,-1 , 0
  4437.9     .05       0  4609.5     .12       0  4643.7     .05       0
  4900.3     .12       0  4953.7     .05       0  4965.1     .05       0
    5009     .05       0  6065.6     .12       0
Bank Sta=4965.1,5009
XS Rating Curve= 0 ,0
Exp/Cntr=0.3,0.1

Type RM Length L Ch R = 1 ,25322   ,1070,1070,1070
BEGIN DESCRIPTION:
Mapping XS 2b00403d
END DESCRIPTION:
XS GIS Cut Line= 4
      2846462.98     10270902.61      2845840.59     10270968.12
      2844743.24     10271279.31        2844221.     10271638.35
#Sta/Elev= 30
    4164 1030.67  4271.9 1030.37    4473 1025.62  4716.5 1029.03  4805.3 1030.56
  4817.4 1023.01  4823.7  1016.3  4836.5 1011.73    4930 1012.05  4947.7 1008.78
  4948.7 1008.28  4991.7 1008.78  4992.4 1010.28  5014.1 1010.79  5081.9 1009.67
  5154.9  1011.4  5179.5 1009.37    5228 1012.36  5252.3 1010.31  5273.1 1012.52
    5325  1013.4  5345.8 1015.75  5413.1 1018.39  5699.2 1017.32  5924.4 1029.41
  6002.6 1029.55  6074.4 1027.16    6370 1031.17  6471.5 1034.26  6564.2 1034.15
#Mann= 5 ,-1 , 0
    4164     .05       0  4716.5     .12       0  4817.4     .05       0
  4947.7     .05       0  4991.7     .05       0
Bank Sta=4947.7,4991.7
XS Rating Curve= 0 ,0
Exp/Cntr=0.3,0.1

Type RM Length L Ch R = 1 ,24252   ,752,752,752
BEGIN DESCRIPTION:
Mapping XS 128ec34e
END DESCRIPTION:
XS GIS Cut Line= 3
      2845644.07     10270591.43      2845136.32     10270345.74
      2843662.24     10270493.15
#Sta/Elev= 30
  4226.9 1028.23    4811 1028.38  4892.1 1024.81  4911.2 1021.14  4932.3 1012.74
  4952.4 1009.16  4954.6 1007.26  4960.5 1002.18  4961.5 1001.68  5004.6 1002.18
  5011.7 1005.34    5063 1004.42  5083.1 1005.63  5103.2 1003.68  5163.5 1005.25
  5193.6 1013.69  5223.8 1017.47    5440 1028.39  5505.2 1032.34  5614.7    1035
  5655.9 1039.64  5686.1 1046.62  5706.1  1046.8  5726.2 1050.01  5774.3 1049.04
  5815.7 1042.59  5866.9 1038.53  5947.3  1035.4    6078 1040.81  6272.4 1042.19
#Mann= 7 ,-1 , 0
  4226.9     .05       0    4811     .12       0  4954.6     .05       0
  4960.5     .05       0  5004.6     .05       0    5440     .12       0
  5774.3     .05       0
Bank Sta=4960.5,5004.6
XS Rating Curve= 0 ,0
Exp/Cntr=0.3,0.1

Type RM Length L Ch R = 1 ,23500   ,811,811,811
BEGIN DESCRIPTION:
Mapping XS 52d4e58d
END DESCRIPTION:
XS GIS Cut Line= 3
        2846119.     10269854.39      2845087.18     10269739.74
      2844153.59     10269313.89
#Sta/Elev= 30
  3779.1 1035.84  3922.4 1040.61  4284.6 1026.57  4440.5 1023.65  4556.7 1024.13
  4596.8 1024.23  4728.4 1020.39  4798.7 1015.29  4829.9 1005.21  4845.8 1007.33
  4868.9 1001.98  4874.4 1005.46    4915 1000.22    4938 1002.76  4972.8 1001.54
  4972.9  996.54  4973.9  996.04  5017.3  996.54  5018.1 1000.67    5041  1001.3
  5081.7  999.97  5156.3 1010.84  5195.7 1019.62  5207.9 1020.51  5225.5 1015.56
    5277 1022.71  5378.8 1025.42  5541.5 1028.61  5765.3 1048.87  5843.4 1048.73
#Mann= 10 ,-1 , 0
  3779.1     .05       0  4440.5     .12       0  4556.7     .05       0
  4596.8     .12       0  4728.4     .05       0  4972.9     .03       0
  5017.3     .05       0    5041     .12       0  5195.7     .05       0
  5378.8     .12       0
Bank Sta=4972.9,5017.3
XS Rating Curve= 0 ,0
Exp/Cntr=0.3,0.1

Type RM Length L Ch R = 1 ,22689   ,884,884,884
BEGIN DESCRIPTION:
Mapping XS c809bec5
END DESCRIPTION:
XS GIS Cut Line= 2
      2845988.03     10269395.82      2844743.22     10268593.24
#Sta/Elev= 30
  4213.9  1029.4  4282.8 1030.07  4391.7 1028.53  4774.8 1019.21  4847.3 1018.68
  4875.5  1019.7  4908.2 1018.24  4918.7 1015.51  4942.2 1003.23  4946.9  993.59
  4947.9  993.09  4991.7  993.59  4999.6  995.41  5013.9  995.58  5026.7  997.74
  5049.6  996.73  5072.2 1000.75  5110.8 1003.51  5131.4 1005.76  5156.7 1009.94
  5208.2 1013.77  5216.1 1015.56  5223.4 1013.51  5301.9 1020.79  5353.4 1020.43
    5432 1022.62  5549.3 1026.72  5571.2 1028.54  5598.3 1028.27    5695 1031.77
#Mann= 7 ,-1 , 0
  4213.9     .05       0  4774.8     .12       0  4908.2     .05       0
  4946.9     .05       0  4991.7     .05       0  5110.8     .12       0
  5131.4     .05       0
Bank Sta=4946.9,4991.7
XS Rating Curve= 0 ,0
Exp/Cntr=0.3,0.1

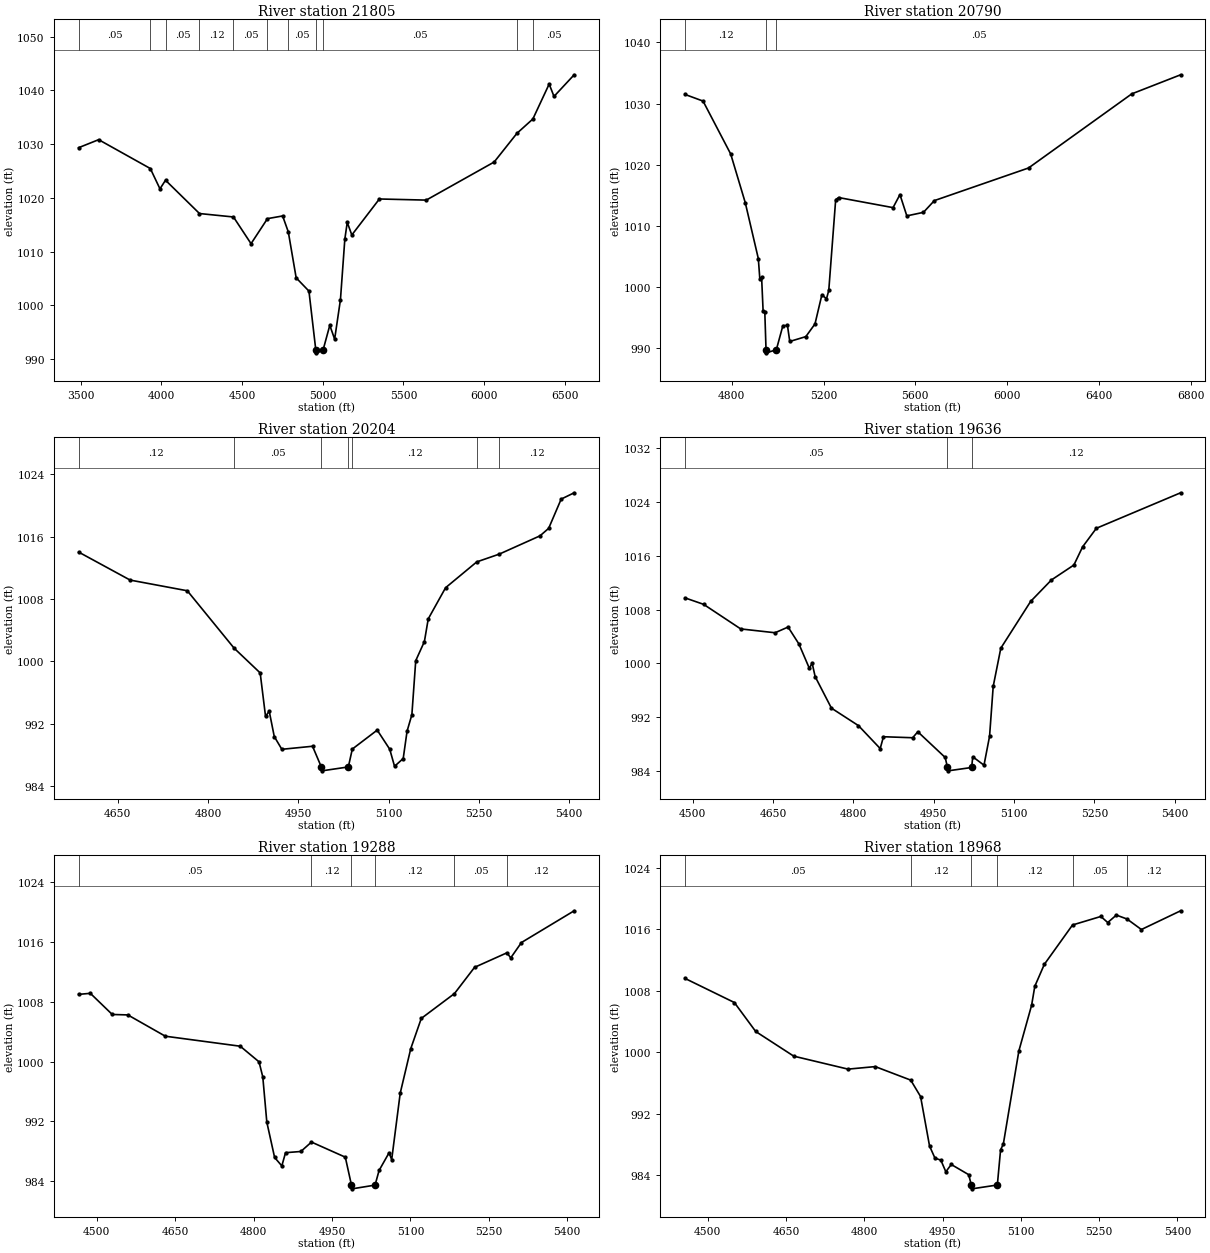
Type RM Length L Ch R = 1 ,21805   ,1015,1015,1015
BEGIN DESCRIPTION:
Mapping XS 6ec60dc5
END DESCRIPTION:
XS GIS Cut Line= 4
      2847200.01     10268871.69      2846037.13     10268380.33
      2845693.18     10268151.04      2844301.04     10268052.77
#Sta/Elev= 30
  3486.8 1029.34  3610.9 1030.83  3931.1 1025.46  3990.9 1021.68  4025.3 1023.28
  4235.9 1017.08  4446.5 1016.44  4555.4 1011.47  4657.2 1016.13  4751.2 1016.63
  4786.4 1013.66  4835.1 1005.11  4914.3 1002.64  4956.9  991.65  4957.9  991.15
  5001.7  991.65  5043.5  996.27  5073.6   993.7  5109.6 1001.06  5136.7 1012.31
  5151.7 1015.44  5180.1 1013.09  5350.9 1019.79  5641.3 1019.58  6062.3 1026.67
  6203.4 1032.01  6302.2 1034.68  6403.2 1041.18  6433.2 1038.88  6558.2 1042.91
#Mann= 11 ,-1 , 0
  3486.8     .05       0  3931.1     .12       0  4025.3     .05       0
  4235.9     .12       0  4446.5     .05       0  4657.2     .12       0
  4786.4     .05       0  4956.9     .05       0  5001.7     .05       0
  6203.4     .12       0  6302.2     .05       0
Bank Sta=4956.9,5001.7
XS Rating Curve= 0 ,0
Exp/Cntr=0.3,0.1

Type RM Length L Ch R = 1 ,20790   ,586,586,586
BEGIN DESCRIPTION:
LITTLE LLANO RIVER 35.0
END DESCRIPTION:
XS GIS Cut Line= 3
       2846405.7     10267603.13      2846138.25       10267301.
      2844382.89     10267348.49
#Sta/Elev= 30
  4596.5 1031.48  4674.7  1030.4  4795.2 1021.75  4858.7 1013.79  4915.6 1004.65
  4922.3 1001.26  4929.9 1001.61  4936.5  996.04  4943.8  995.97  4949.2  989.74
  4950.2  989.24  4994.1  989.74  5022.6  993.68  5042.6  993.71  5052.6   991.1
  5122.6  991.89  5162.6  993.97  5192.6  998.74  5212.6  998.07  5222.6  999.44
  5252.7 1014.28  5265.3 1014.63  5502.7 1012.98  5532.8 1015.11  5562.8 1011.63
  5635.2 1012.21  5682.8 1014.13    6093 1019.46  6543.1 1031.58    6756  1034.7
#Mann= 3 ,-1 , 0
  4596.5     .12       0  4949.2     .05       0  4994.1     .05       0
Bank Sta=4949.2,4994.1
XS Rating Curve= 0 ,0
Exp/Cntr=0.3,0.1

Type RM Length L Ch R = 1 ,20204   ,568,568,568
BEGIN DESCRIPTION:
LITTLE LLANO RIVER 34.0
END DESCRIPTION:
XS GIS Cut Line= 3
      2846405.69     10266953.12        2846061.       10266722.
      2845805.69     10266403.12
#Sta/Elev= 30
    4585 1014.01  4670.6 1010.42  4765.6 1009.05  4843.3  1001.7  4886.7  998.52
  4895.6  992.95  4901.7  993.62  4910.1  990.37  4922.7  988.73  4973.7  989.12
  4988.3  986.47  4989.3  985.97  5033.2  986.47  5039.8  988.76  5081.2  991.19
    5102  988.74    5110  986.55  5124.4  987.55  5130.8  991.05  5138.8  993.17
  5145.2 1000.09  5159.6 1002.54    5166 1005.45  5194.8 1009.44  5246.6 1012.75
  5284.1 1013.75  5351.7 1016.09  5366.1 1017.05  5386.9  1020.8  5408.5 1021.61
#Mann= 7 ,-1 , 0
    4585     .12       0  4843.3     .05       0  4988.3     .05       0
  5033.2     .05       0  5039.8     .12       0  5246.6     .05       0
  5284.1     .12       0
Bank Sta=4988.3,5033.2
XS Rating Curve= 0 ,0
Exp/Cntr=0.3,0.1

Type RM Length L Ch R = 1 ,19636   ,348,348,348
BEGIN DESCRIPTION:
LITTLE LLANO RIVER 33.0
END DESCRIPTION:
XS GIS Cut Line= 3
      2846705.73     10266253.12       2846197.5       10266177.
      2845805.72     10266053.12
#Sta/Elev= 30
  4486.1 1009.74  4520.7 1008.78  4589.9 1005.12    4654 1004.55  4678.3  1005.4
  4698.5 1002.88  4718.1  999.23  4723.1 1000.05  4728.8  998.02  4759.2  993.32
  4809.7  990.71  4850.2   987.3  4856.3  989.06  4910.8  988.91  4920.4   989.8
  4971.5  985.97  4975.8  984.48  4976.8  983.98  5020.9  984.48  5022.9  986.08
  5043.9  984.82  5054.3  989.13  5061.1  996.56  5075.3 1002.25    5131 1009.22
  5169.7 1012.41  5211.7 1014.64  5227.9 1017.34  5253.6 1020.11  5410.9  1025.4
#Mann= 3 ,-1 , 0
  4486.1     .05       0  4975.8     .07       0  5020.9     .12       0
Bank Sta=4975.8,5020.9
XS Rating Curve= 0 ,0
Exp/Cntr=0.3,0.1

Type RM Length L Ch R = 1 ,19288   ,320,320,320
BEGIN DESCRIPTION:
LITTLE LLANO RIVER 32.0
END DESCRIPTION:
XS GIS Cut Line= 3
      2846755.72     10266153.14       2846315.5       10265850.
      2845905.73     10265903.11
#Sta/Elev= 30
  4465.5 1009.01  4487.9 1009.15  4529.8 1006.32  4559.6 1006.26  4631.3 1003.41
  4774.6 1002.07  4810.5  999.98  4817.7  997.96  4825.4  991.91  4840.3  987.18
  4854.1  986.05  4861.2  987.82  4890.5  987.98  4910.8  989.24  4975.5  987.22
  4987.3  983.48  4988.3  982.98  5032.4  983.48  5040.1  985.44  5059.2  987.81
  5064.2  986.89  5080.5  995.78  5100.7 1001.75  5120.8 1005.79  5184.3 1009.12
  5222.7 1012.63  5284.5 1014.57  5291.9  1013.9  5312.4 1015.95  5413.2  1020.2
#Mann= 6 ,-1 , 0
  4465.5     .05       0  4910.8     .12       0  4987.3     .07       0
  5032.4     .12       0  5184.3     .05       0  5284.5     .12       0
Bank Sta=4987.3,5032.4
XS Rating Curve= 0 ,0
Exp/Cntr=0.3,0.1

Type RM Length L Ch R = 1 ,18968   ,793,793,793
BEGIN DESCRIPTION:
LITTLE LLANO RIVER 31.0
END DESCRIPTION:
XS GIS Cut Line= 3
      2846955.68     10265703.11       2846433.5       10265552.
      2846055.68     10265403.11
#Sta/Elev= 30
  4456.4 1009.59  4550.8 1006.46  4591.7 1002.69  4664.6  999.48  4768.7  997.79
  4820.8  998.12  4888.8  996.36  4907.7  994.22  4924.9  987.78  4935.3   986.2
  4946.5  985.95  4956.1  984.43  4966.5  985.38    5000  984.05  5004.9  982.71
  5005.9  982.21  5054.8  982.71    5061  987.28  5066.3  988.04  5096.1 1000.17
  5120.5 1006.11  5126.6 1008.57  5144.9 1011.43  5198.9 1016.55  5253.2 1017.66
  5266.4 1016.87  5282.9 1017.84  5303.3 1017.33  5330.9 1015.96  5406.1  1018.4
#Mann= 6 ,-1 , 0
  4456.4     .05       0  4888.8     .12       0  5004.9     .07       0
  5054.8     .12       0  5198.9     .05       0  5303.3     .12       0
Bank Sta=5004.9,5054.8
XS Rating Curve= 0 ,0
Exp/Cntr=0.3,0.1

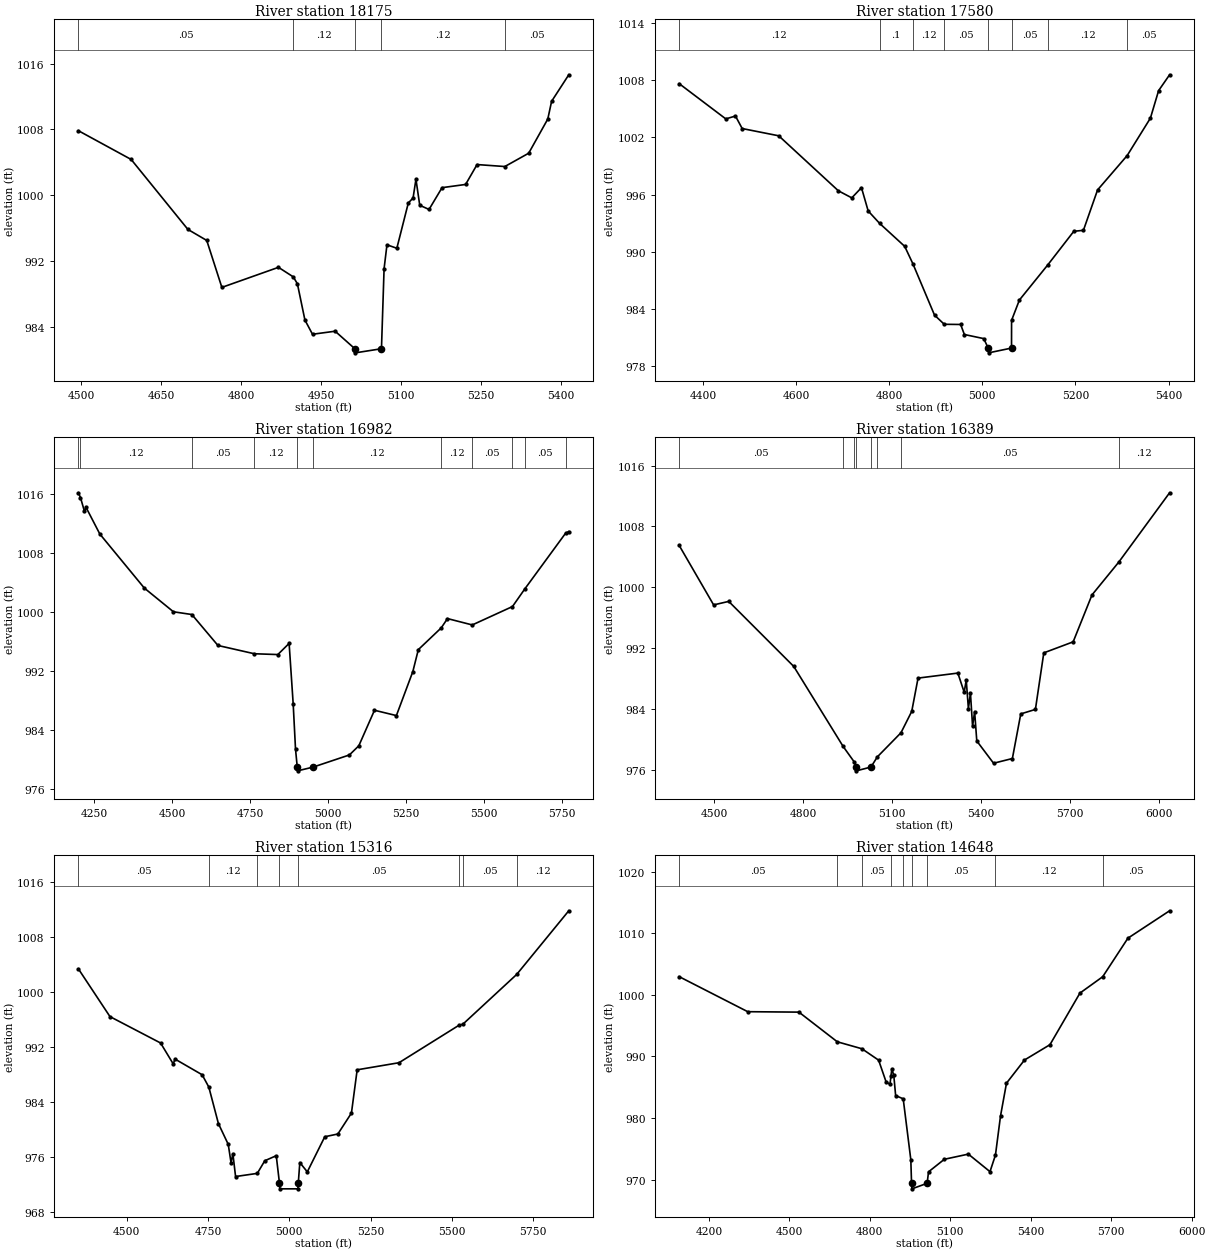
Type RM Length L Ch R = 1 ,18175   ,595,595,595
BEGIN DESCRIPTION:
LITTLE LLANO RIVER 29.0
END DESCRIPTION:
XS GIS Cut Line= 3
      2847155.71     10265203.13      2846791.25       10264854.
      2846405.72     10264703.13
#Sta/Elev= 30
  4495.3 1007.84  4594.2 1004.34  4700.5  995.83  4735.8  994.49  4764.1  988.78
  4870.1  991.22  4897.9  990.06  4905.6  989.22  4919.7  984.81  4933.9  983.08
  4976.3  983.45  5013.2  981.32  5014.2  980.82  5063.1  981.32    5068  991.05
  5073.4  993.96  5091.9  993.54  5113.4  999.05  5122.3  999.65  5127.7 1001.93
  5134.8  998.77  5152.2  998.26  5176.6 1000.91  5220.7  1001.3  5242.2 1003.72
  5294.2 1003.48  5338.9  1005.1  5374.7 1009.26  5381.8 1011.41    5414 1014.64
#Mann= 5 ,-1 , 0
  4495.3     .05       0  4897.9     .12       0  5013.2     .07       0
  5063.1     .12       0  5294.2     .05       0
Bank Sta=5013.2,5063.1
XS Rating Curve= 0 ,0
Exp/Cntr=0.3,0.1

Type RM Length L Ch R = 1 ,17580   ,598,598,598
BEGIN DESCRIPTION:
LITTLE LLANO RIVER 28.0
END DESCRIPTION:
XS GIS Cut Line= 3
      2847605.68     10264753.11      2847096.75       10264347.
      2846705.66     10264253.11
#Sta/Elev= 30
  4348.9 1007.61    4449 1003.92  4469.8 1004.22  4484.2 1002.91  4562.7 1002.15
  4690.8  996.39  4719.6  995.65  4740.4  996.72  4754.8  994.28  4779.3  992.98
  4833.3  990.57    4851  988.73  4897.3  983.37  4918.2  982.41  4953.4  982.39
  4961.4  981.34  5003.1  980.91  5012.5  979.92  5013.5  979.42  5062.7  979.92
  5062.8  982.82  5079.6  984.95  5140.4  988.62  5196.5  992.15  5217.1  992.25
  5247.5  996.48  5311.1 1000.08    5361    1004  5378.6 1006.88  5402.2 1008.54
#Mann= 8 ,-1 , 0
  4348.9     .12       0  4779.3      .1       0    4851     .12       0
  4918.2     .05       0  5012.5     .05       0  5062.7     .05       0
  5140.4     .12       0  5311.1     .05       0
Bank Sta=5012.5,5062.7
XS Rating Curve= 0 ,0
Exp/Cntr=0.3,0.1

Type RM Length L Ch R = 1 ,16982   ,593,593,593
BEGIN DESCRIPTION:
LITTLE LLANO RIVER 27.0
END DESCRIPTION:
XS GIS Cut Line= 3
      2848055.67     10263953.11      2847273.75       10263784.
      2846505.65     10263853.11
#Sta/Elev= 30
    4200  1016.1  4206.8 1015.45  4219.5 1013.58  4224.6 1014.12  4268.7 1010.52
  4411.3  1003.2  4504.6  999.99  4563.6  999.62  4647.2  995.43  4763.8  994.31
    4839   994.2  4875.2  995.71  4888.3  987.48  4895.7  981.39  4901.3  978.96
  4902.3  978.46  4951.6  978.96  5068.3  980.61  5098.5  981.85  5148.7  986.66
  5218.9  985.94  5271.6   991.9  5289.2  994.87  5362.5  997.81  5382.6  999.07
    5462  998.21  5590.8  1000.7  5630.4 1003.09  5760.7 1010.61  5771.2 1010.85
#Mann= 11 ,-1 , 0
    4200     .05       0  4206.8     .12       0  4563.6     .05       0
  4763.8     .12       0  4901.3     .07       0  4951.6     .12       0
  5362.5     .12       0    5462     .05       0  5590.8     .12       0
  5630.4     .05       0  5760.7     .12       0
Bank Sta=4901.3,4951.6
XS Rating Curve= 0 ,0
Exp/Cntr=0.3,0.1

Type RM Length L Ch R = 1 ,16389   ,1073,1073,1073
BEGIN DESCRIPTION:
LITTLE LLANO RIVER 26.0
END DESCRIPTION:
XS GIS Cut Line= 3
      2847955.72     10263403.13        2847371.       10263204.
      2846655.66     10262453.09
#Sta/Elev= 30
  4382.3  1005.5  4498.5  997.68  4549.5  998.14    4769  989.58  4935.5  979.06
  4973.5  976.99  4979.1  976.35  4980.1  975.85  5029.4  976.35    5051  977.69
  5130.7  980.86    5167  983.67  5188.3  988.05  5322.6  988.71    5344  986.19
  5350.9  987.79  5358.2  984.04  5365.1  986.08  5372.3  981.71  5379.2  983.65
  5386.5  979.78  5443.1  976.85  5506.6  977.47  5534.9  983.34  5584.3  983.93
  5612.6  991.37  5711.7  992.82  5775.2  998.99    5866 1003.33  6037.1 1012.43
#Mann= 8 ,-1 , 0
  4382.3     .05       0  4935.5     .12       0  4973.5     .05       0
  4979.1     .05       0  5029.4     .05       0    5051     .12       0
  5130.7     .05       0    5866     .12       0
Bank Sta=4979.1,5029.4
XS Rating Curve= 0 ,0
Exp/Cntr=0.3,0.1

Type RM Length L Ch R = 1 ,15316   ,668,668,668
BEGIN DESCRIPTION:
LITTLE LLANO RIVER 24.0
END DESCRIPTION:
XS GIS Cut Line= 3
      2848055.66      10262453.1      2847478.75       10262158.
      2846655.67     10262403.12
#Sta/Elev= 30
    4352 1003.37  4449.1  996.42  4604.6  992.58  4643.4  989.54    4649  990.24
  4732.3  987.96  4752.8  986.17  4782.3  980.85  4812.5  977.83  4821.1  975.15
  4826.7  976.48    4835  973.15  4901.8  973.61  4924.8  975.45    4960  976.18
  4969.7  972.26  4971.1  971.36  5026.5  971.36  5027.8  972.26  5032.4  975.18
  5055.4  973.83  5109.1  978.94  5149.3  979.34    5191  982.38  5208.6  988.68
  5337.1  989.71  5522.7   995.2  5532.8  995.29  5698.8 1002.56  5858.8 1011.82
#Mann= 8 ,-1 , 0
    4352     .05       0  4752.8     .12       0  4901.8     .05       0
  4969.7     .05       0  5027.8     .05       0  5522.7     .12       0
  5532.8     .05       0  5698.8     .12       0
Bank Sta=4969.7,5027.8
XS Rating Curve= 0 ,0
Exp/Cntr=0.3,0.1

Type RM Length L Ch R = 1 ,14648   ,1184,1184,1184
BEGIN DESCRIPTION:
Mapping XS be20f9de
END DESCRIPTION:
XS GIS Cut Line= 3
      2848461.17     10262288.93      2847836.14     10261643.06
      2847004.49     10261227.23
#Sta/Elev= 30
  4089.1 1002.95  4344.7  997.26  4535.6  997.19  4678.7  992.37  4770.5  991.24
  4832.7  989.39    4861  985.81  4875.1  985.48  4878.8  986.81  4882.1  987.99
  4889.3   986.9  4896.2  983.64  4924.4  983.11  4952.8  973.22  4955.5  969.39
  4956.9  968.49  5013.7  969.39  5018.8  971.25  5077.8  973.29  5167.3  974.13
    5248  971.28  5268.4  973.98  5287.2  980.31  5309.5  985.65  5376.6  989.41
  5471.6   991.9  5583.4 1000.28  5668.3 1002.94  5762.3  1009.2  5917.7 1013.65
#Mann= 9 ,-1 , 0
  4089.1     .05       0  4678.7     .12       0  4770.5     .05       0
  4878.8     .12       0  4924.4     .05       0  4955.5     .05       0
  5013.7     .05       0  5268.4     .12       0  5668.3     .05       0
Bank Sta=4955.5,5013.7
XS Rating Curve= 0 ,0
Exp/Cntr=0.3,0.1

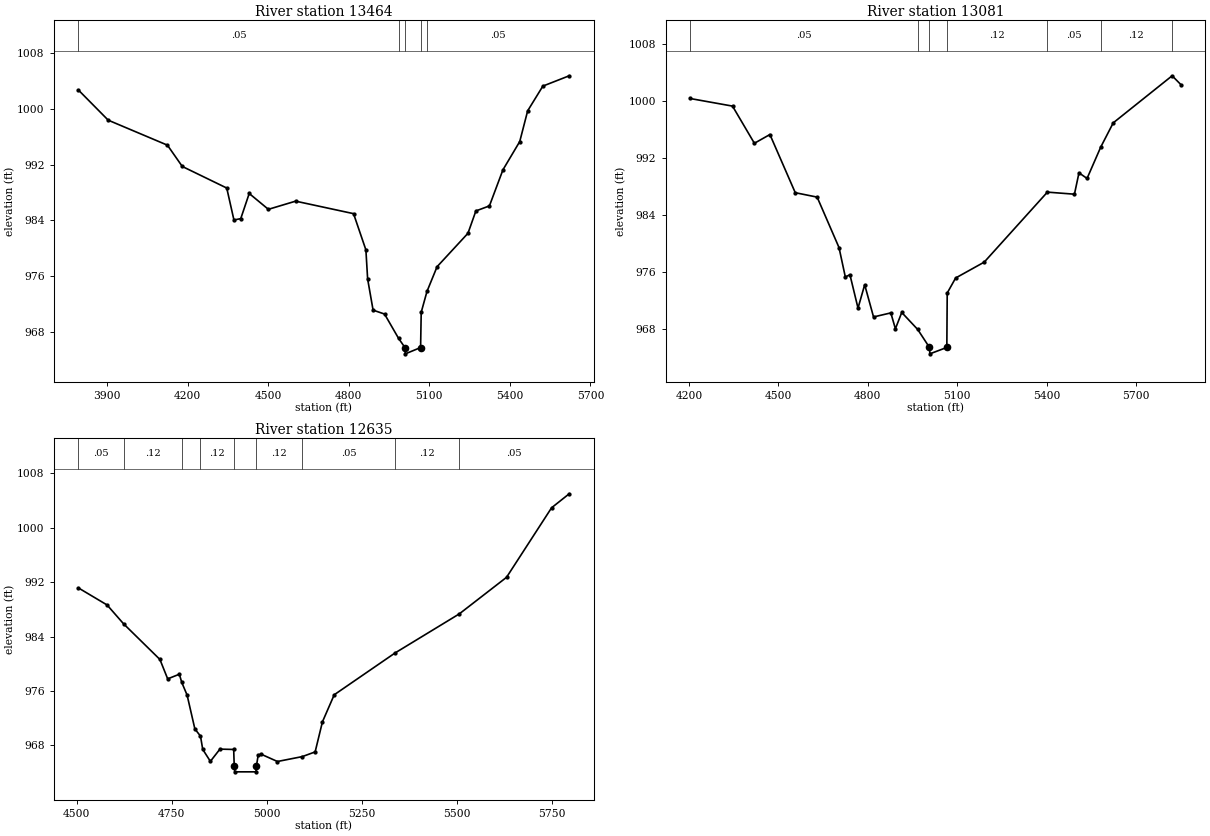
Type RM Length L Ch R = 1 ,13464   ,383,383,383
BEGIN DESCRIPTION:
Mapping XS 207eea47
END DESCRIPTION:
XS GIS Cut Line= 3
      2848898.63     10262038.85      2848502.81     10260809.73
       2848190.5     10260372.49
#Sta/Elev= 30
  3792.5 1002.68  3903.6  998.36  4124.2  994.78  4179.6  991.73  4345.2  988.64
    4372  984.06  4397.4  984.26  4428.9  987.86  4500.3  985.59  4601.8  986.76
  4817.6  984.97  4863.6  979.78  4870.1  975.61  4890.4  971.15  4933.1  970.59
  4985.3  967.11  5009.1  965.79  5010.5  964.89  5067.4  965.79  5069.7  970.84
  5091.2  973.83  5128.8  977.37  5243.9  982.16  5273.4  985.36  5323.8  986.08
  5374.2  991.25  5436.8   995.3  5466.3   999.7  5522.9 1003.24  5621.1 1004.72
#Mann= 5 ,-1 , 0
  3792.5     .05       0  4985.3     .12       0  5009.1     .07       0
  5067.4     .12       0  5091.2     .05       0
Bank Sta=5009.1,5067.4
XS Rating Curve= 0 ,0
Exp/Cntr=0.3,0.1

Type RM Length L Ch R = 1 ,13081   ,446,446,446
BEGIN DESCRIPTION:
Mapping XS e59192b8
END DESCRIPTION:
XS GIS Cut Line= 3
      2849273.64     10261372.23      2848773.64     10260559.73
      2848190.48     10260184.84
#Sta/Elev= 30
  4203.4 1000.36  4345.9  999.29  4419.3  994.07  4471.4   995.3  4556.5  987.13
  4629.9  986.51  4703.3  979.43  4724.5   975.3    4740  975.61  4767.1  970.92
  4789.5   974.2  4819.2  969.68  4877.2  970.25  4892.6  968.02  4913.9  970.31
  4967.5  967.92  5006.9   965.4  5008.3   964.5  5065.2   965.4  5066.5  973.04
  5094.7  975.15  5190.7  977.38  5402.7  987.21  5493.5  986.92  5508.7  989.92
  5535.8  989.13  5581.7  993.53  5623.7  996.94  5821.4 1003.55  5850.7 1002.31
#Mann= 7 ,-1 , 0
  4203.4     .05       0  4967.5     .12       0  5006.9     .07       0
  5065.2     .12       0  5402.7     .05       0  5581.7     .12       0
  5821.4     .05       0
Bank Sta=5006.9,5065.2
XS Rating Curve= 0 ,0
Exp/Cntr=0.3,0.1

Type RM Length L Ch R = 1 ,12635   ,728,728,728
BEGIN DESCRIPTION:
LITTLE LLANO RIVER 19.0
END DESCRIPTION:
XS GIS Cut Line= 3
      2849255.68     10260853.11      2849155.75       10260368.
      2848405.65      10260103.1
#Sta/Elev= 30
  4504.7  991.16  4580.2  988.65  4623.4  985.89  4719.1  980.64  4739.5  977.79
  4770.2  978.47  4776.6  977.26  4790.6   975.4    4811  970.43  4825.8  969.37
  4831.7  967.42  4851.8  965.66  4876.9  967.46  4913.1  967.41  4914.5  965.02
  4915.9  964.12  4971.6  964.12    4973  965.02  4977.5  966.55  4984.6  966.73
  5028.1  965.64  5093.5  966.36  5127.3  967.05  5146.5  971.47  5177.5  975.45
  5337.6   981.6  5506.4  987.34  5630.7  992.72  5749.1 1002.94  5795.5    1005
#Mann= 9 ,-1 , 0
  4504.7     .05       0  4623.4     .12       0  4776.6     .05       0
  4825.8     .12       0  4914.5     .07       0    4973     .12       0
  5093.5     .05       0  5337.6     .12       0  5506.4     .05       0
Bank Sta=4914.5,4973
XS Rating Curve= 0 ,0
Exp/Cntr=0.3,0.1