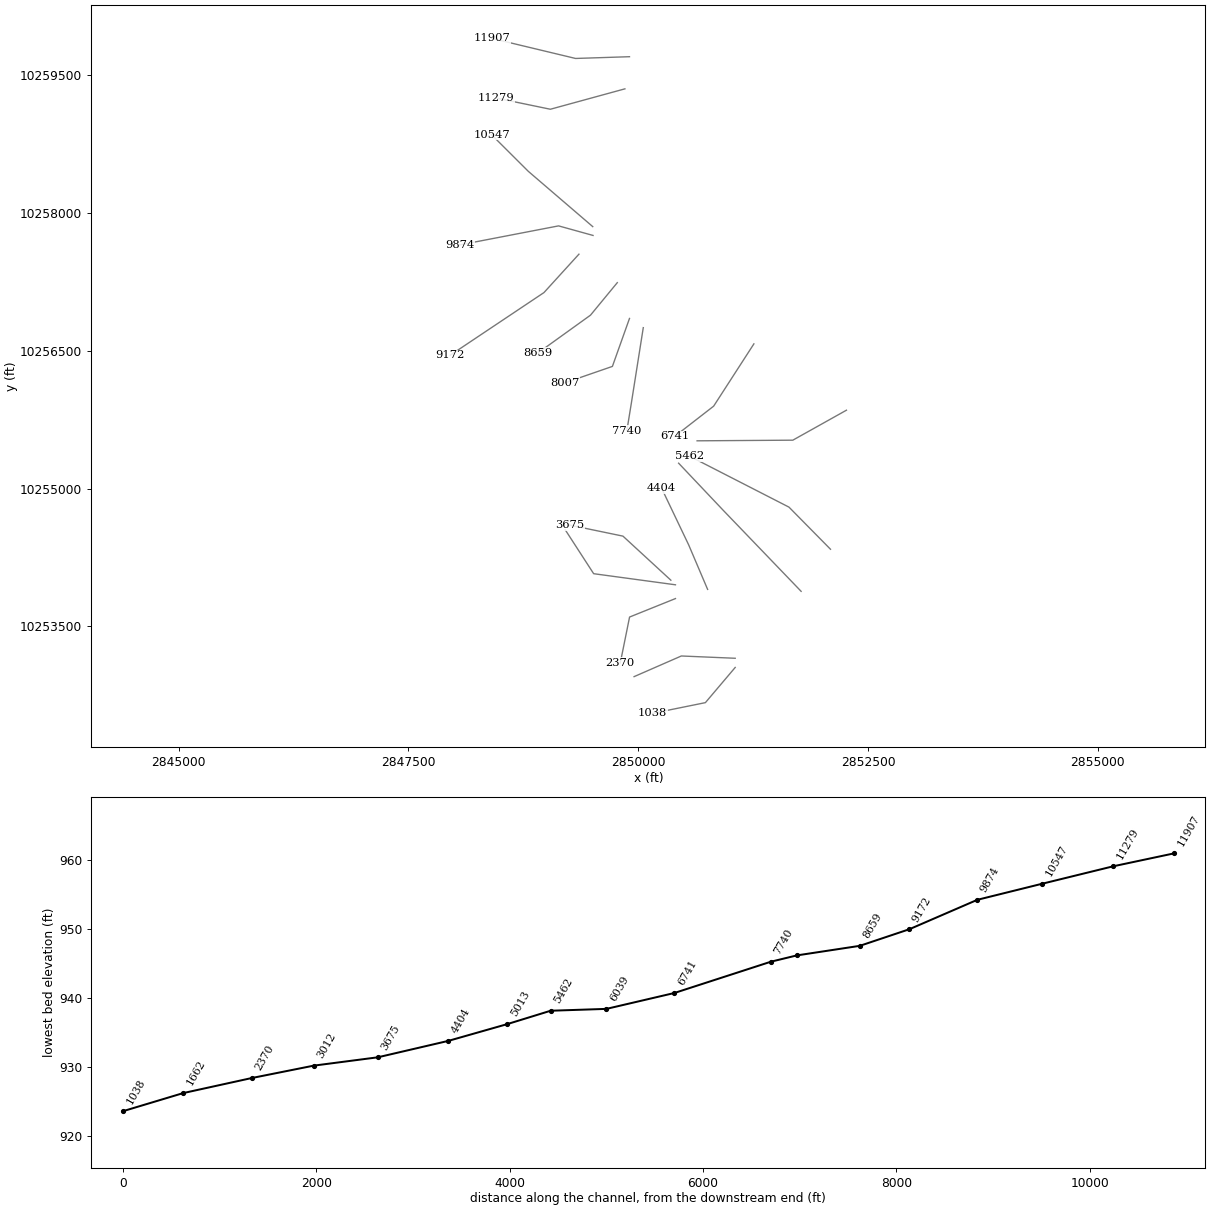
HEC-RAS study LITTLE LLANO RIVER.prj: LITTLE LLANO RIVER Base Level Engineering

--- LITTLE LLANO RIVER.g01 (geometry) --- (continued)

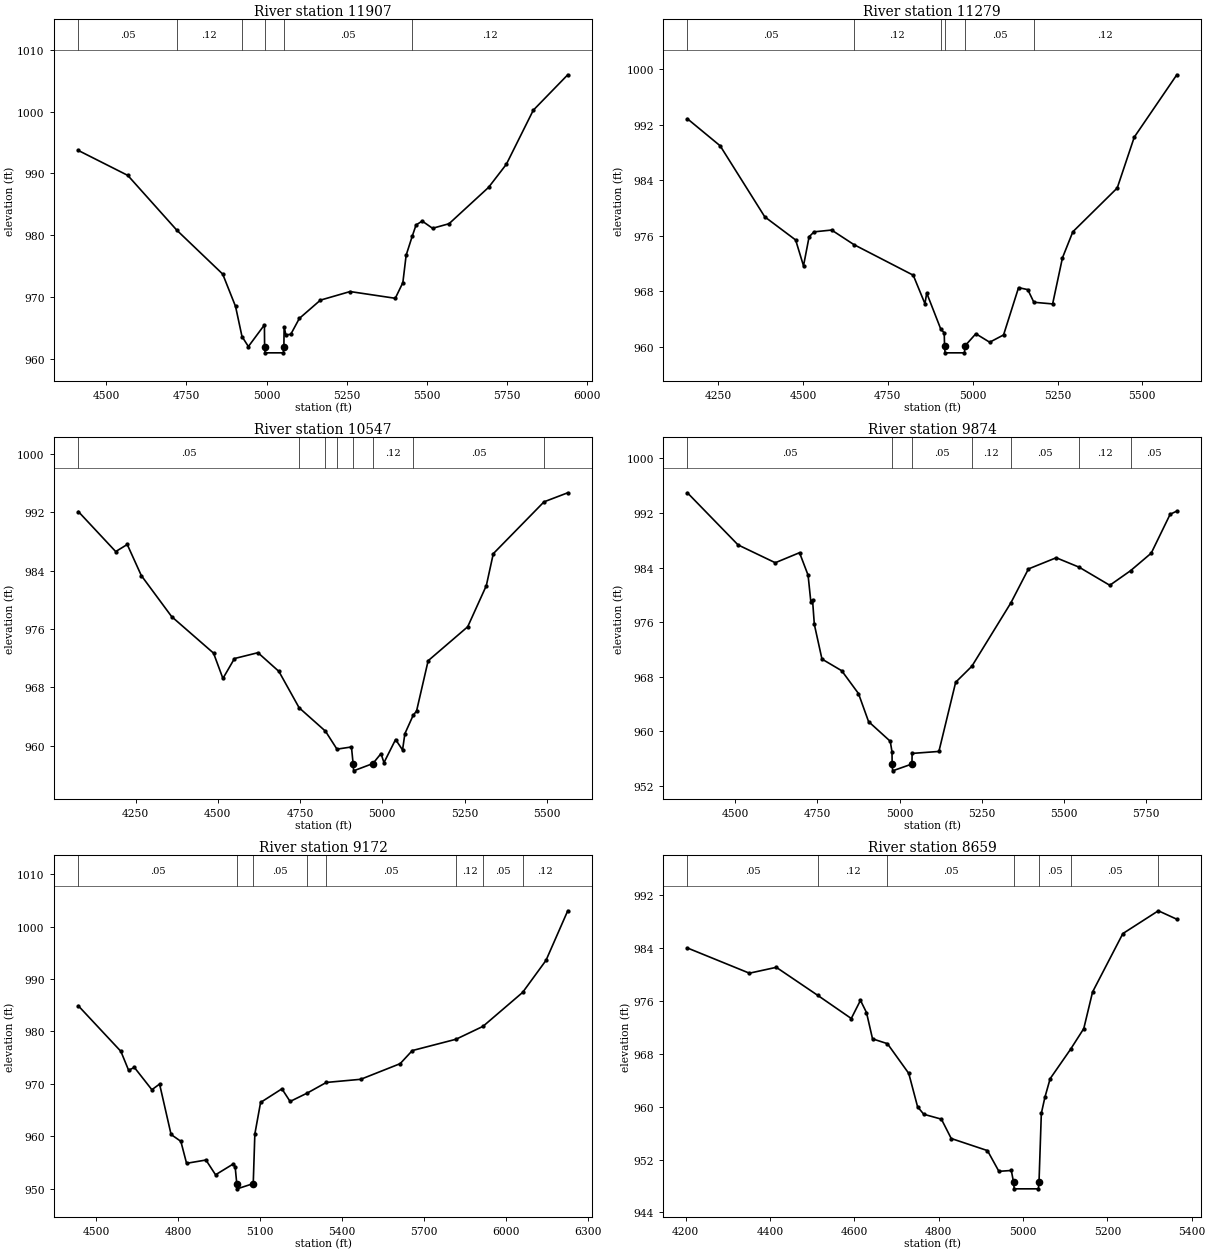
Type RM Length L Ch R = 1 ,11907   ,628,628,628
BEGIN DESCRIPTION:
LITTLE LLANO RIVER 18.0
END DESCRIPTION:
XS GIS Cut Line= 3
      2849905.69     10259703.11        2849319.       10259684.
      2848405.71      10259903.1
#Sta/Elev= 30
    4413  993.73  4567.3  989.69  4720.2  980.82  4863.2  973.72  4903.3  968.48
  4923.4  963.61  4943.3  961.99  4993.3  965.49  4993.9  961.97  4995.4  960.97
  5052.5  960.97    5054  961.97  5054.8  965.19  5060.2  963.89  5075.4  963.96
  5102.2  966.54  5167.9   969.5  5260.5  970.89  5401.4   969.8    5425  972.33
  5435.3  976.78  5454.1  979.82  5466.2  981.67  5485.4   982.3  5517.6  981.13
    5569  981.87  5692.4  987.76  5747.7  991.49  5831.7 1000.24  5939.2 1005.98
#Mann= 6 ,-1 , 0
    4413     .05       0  4720.2     .12       0  4923.4     .05       0
  4993.9     .05       0    5054     .05       0  5454.1     .12       0
Bank Sta=4993.9,5054
XS Rating Curve= 0 ,0
Exp/Cntr=0.3,0.1

Type RM Length L Ch R = 1 ,11279   ,732,732,732
BEGIN DESCRIPTION:
LITTLE LLANO RIVER 17.0
END DESCRIPTION:
XS GIS Cut Line= 3
      2849855.68     10259353.11      2849044.75       10259131.
      2848455.67     10259253.11
#Sta/Elev= 30
  4159.2  992.84  4255.8  988.94  4387.3   978.7  4478.2  975.37  4501.4  971.64
  4517.9  975.83  4532.5  976.54  4584.3   976.8    4650   974.7  4824.8  970.29
  4859.3  966.18  4864.5  967.72  4906.3  962.48  4916.1     962  4917.1   960.1
  4918.6   959.1  4975.8   959.1  4977.3   960.1  5009.3  961.85  5050.1  960.63
    5091  961.68  5135.2   968.5  5162.4  968.21  5180.3  966.39  5235.6  966.15
  5264.6   972.8  5295.2  976.55    5426  982.86  5476.2  990.19  5601.6  999.18
#Mann= 6 ,-1 , 0
  4159.2     .05       0    4650     .12       0  4906.3     .05       0
  4917.1     .05       0  4977.3     .05       0  5180.3     .12       0
Bank Sta=4917.1,4977.3
XS Rating Curve= 0 ,0
Exp/Cntr=0.3,0.1

Type RM Length L Ch R = 1 ,10547   ,673,673,673
BEGIN DESCRIPTION:
LITTLE LLANO RIVER 16.0
END DESCRIPTION:
XS GIS Cut Line= 3
      2849505.69     10257853.11      2848804.75       10258455.
      2848405.68     10258853.12
#Sta/Elev= 30
  4076.1  992.09  4189.7  986.61  4224.8  987.58  4267.6  983.32  4359.8   977.7
  4487.1   972.7  4515.6  969.23  4550.7  971.96  4622.1  972.76  4685.7   970.2
  4747.2  965.22  4827.3  962.01  4862.2  959.55  4906.3  959.85  4911.3  957.58
  4912.8  956.58  4971.5  957.58  4996.1  958.94  5005.1   957.7  5040.4  960.87
  5061.6  959.44  5068.7  961.67  5093.9  964.19  5104.1  964.76  5139.4  971.66
  5259.6  976.31  5316.2  981.94  5337.4  986.32  5491.6  993.42  5563.7  994.66
#Mann= 8 ,-1 , 0
  4076.1     .05       0  4747.2     .12       0  4827.3     .05       0
  4862.2     .12       0  4911.3     .07       0  4971.5     .12       0
  5093.9     .05       0  5491.6     .12       0
Bank Sta=4911.3,4971.5
XS Rating Curve= 0 ,0
Exp/Cntr=0.3,0.1

Type RM Length L Ch R = 1 ,9874    ,702,702,702
BEGIN DESCRIPTION:
LITTLE LLANO RIVER 15.0
END DESCRIPTION:
XS GIS Cut Line= 3
      2849509.14      10257756.9      2849134.12     10257861.08
      2848055.71     10257653.12
#Sta/Elev= 30
  4355.3  994.94  4509.3  987.31  4622.4   984.7  4696.1  986.17  4722.1  982.88
  4730.4  979.02  4735.6  979.29  4741.1  975.68  4764.3   970.6  4824.4  968.89
  4875.3  965.55  4905.9  961.45  4971.8  958.57  4977.2  957.02  4977.6  955.24
  4979.1  954.24  5037.8  955.24  5038.3  956.79  5119.7  957.08  5170.7  967.21
  5219.9  969.55  5338.5  978.83  5391.8  983.79  5476.2  985.43  5545.9  984.05
  5639.1   981.4  5702.1  983.53    5765   986.1  5822.5  991.79  5842.8  992.26
#Mann= 7 ,-1 , 0
  4355.3     .05       0  4977.6     .05       0  5037.8     .05       0
  5219.9     .12       0  5338.5     .05       0  5545.9     .12       0
  5702.1     .05       0
Bank Sta=4977.6,5037.8
XS Rating Curve= 0 ,0
Exp/Cntr=0.3,0.1

Type RM Length L Ch R = 1 ,9172    ,513,513,513
BEGIN DESCRIPTION:
LITTLE LLANO RIVER 14.0
END DESCRIPTION:
XS GIS Cut Line= 3
      2849355.69     10257553.12      2848975.25       10257135.
      2847955.66      10256453.1
#Sta/Elev= 30
  4434.7   984.9  4590.5  976.21  4618.8   972.6  4639.8  973.15    4704  968.89
  4732.2  969.97  4774.3  960.35  4810.1  959.04    4831  954.85    4902  955.48
  4937.1  952.66  5002.7  954.75  5008.9   954.2  5014.8  950.98  5016.3  949.98
  5075.1  950.98    5081  960.44    5102  966.46  5180.1  969.06  5210.1  966.65
  5273.5  968.27  5342.8  970.28  5468.7  970.88    5613  973.86  5657.5  976.36
  5817.5  978.52  5916.3  980.98  6061.5  987.46    6147  993.57  6226.6 1003.03
#Mann= 8 ,-1 , 0
  4434.7     .05       0  5014.8     .05       0  5075.1     .05       0
  5273.5     .12       0  5342.8     .05       0  5817.5     .12       0
  5916.3     .05       0  6061.5     .12       0
Bank Sta=5014.8,5075.1
XS Rating Curve= 0 ,0
Exp/Cntr=0.3,0.1

Type RM Length L Ch R = 1 ,8659    ,652,652,652
BEGIN DESCRIPTION:
LITTLE LLANO RIVER 13.0
END DESCRIPTION:
XS GIS Cut Line= 3
      2849772.98     10257242.99      2849481.34     10256888.86
      2848911.88     10256479.13
#Sta/Elev= 30
  4204.4  984.04  4351.4  980.22  4415.2  981.11  4513.3  976.87  4592.9  973.36
  4614.7  976.11    4629  974.26  4643.3  970.28  4678.6  969.55  4729.2  965.05
  4750.1     960  4764.8  958.86  4806.6  958.12  4829.9  955.19  4915.8  953.36
  4942.9  950.22  4972.3  950.35  4977.7  948.57  4979.2  947.57  5036.5  947.57
    5038  948.57  5043.5  958.99    5052  961.44  5064.4  964.25  5113.1  968.73
  5144.1  971.83    5165  977.38  5236.8  986.22  5320.9  989.67  5364.7  988.39
#Mann= 7 ,-1 , 0
  4204.4     .05       0  4513.3     .12       0  4678.6     .05       0
  4977.7     .03       0    5038     .05       0  5113.1     .05       0
  5320.9     .12       0
Bank Sta=4977.7,5038
XS Rating Curve= 0 ,0
Exp/Cntr=0.3,0.1

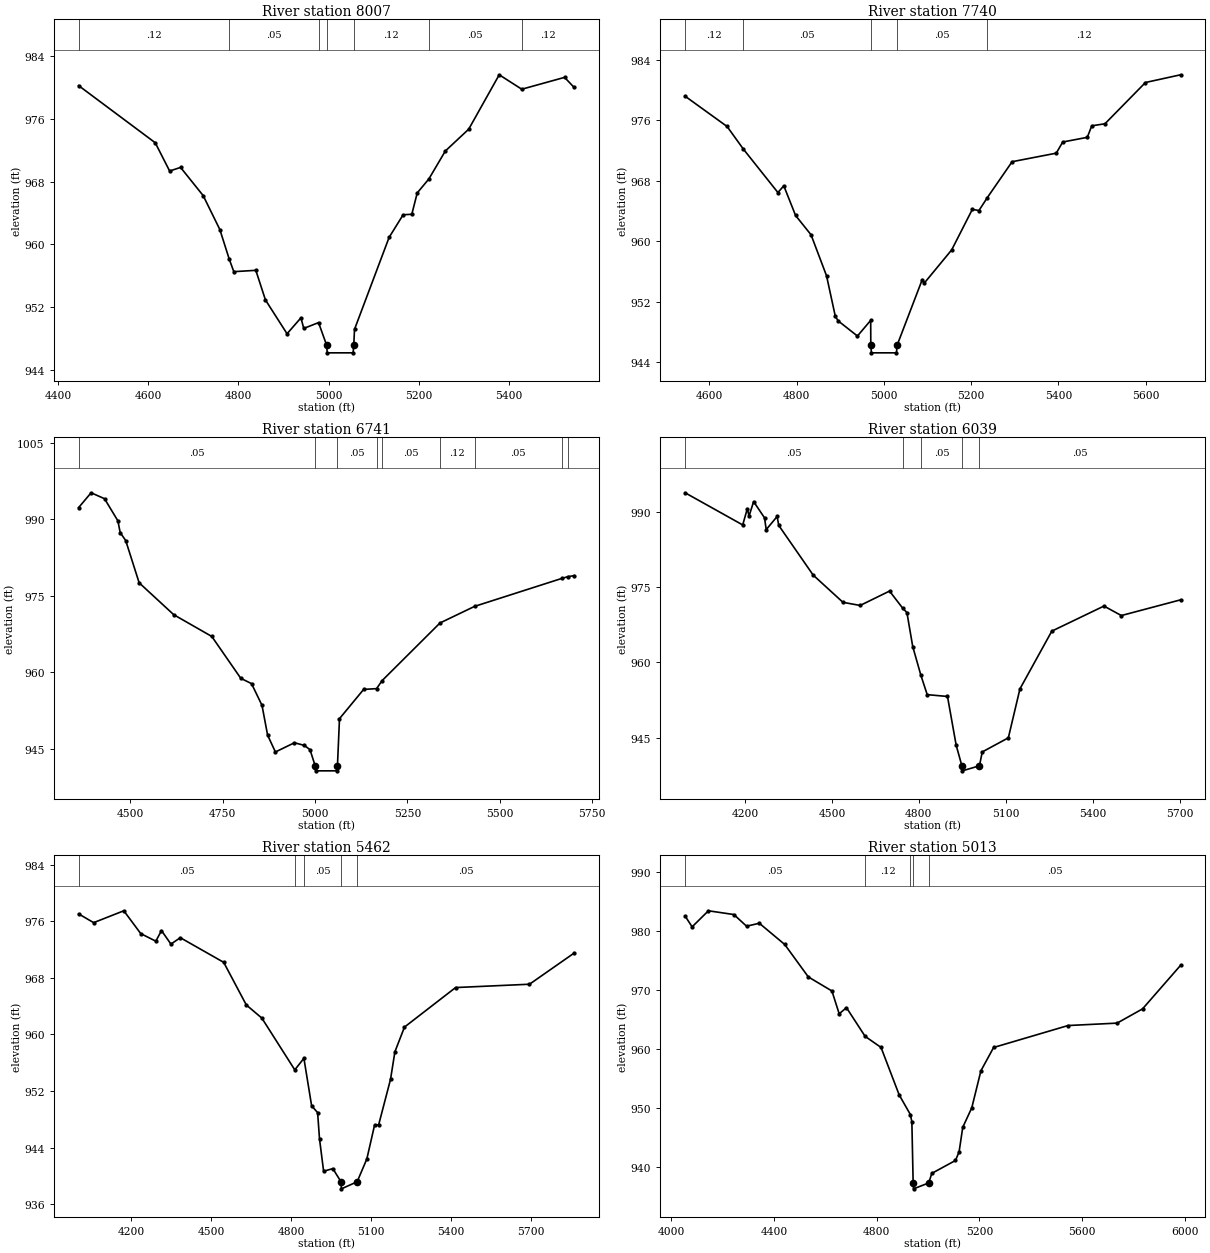
Type RM Length L Ch R = 1 ,8007    ,267,267,267
BEGIN DESCRIPTION:
LITTLE LLANO RIVER 12.0
END DESCRIPTION:
XS GIS Cut Line= 3
      2849905.67     10256853.08      2849719.75       10256331.
      2849205.66      10256153.1
#Sta/Elev= 30
  4445.8  980.22  4615.6  972.94  4647.5  969.34  4671.7   969.8  4721.8  966.21
  4758.8  961.88  4779.6  958.11  4789.7  956.52  4838.5  956.69  4859.8  952.92
  4907.7  948.61  4938.5  950.64  4944.7  949.29  4977.5  950.03  4995.3  947.18
  4996.8  946.18  5054.1  946.18  5055.6  947.18  5057.2  949.17  5133.9  960.89
    5165  963.77  5184.2  963.83  5196.2  966.55    5222  968.33  5258.5  971.89
  5310.3  974.67  5377.9   981.6  5427.9  979.76  5522.8  981.27    5544  979.98
#Mann= 7 ,-1 , 0
  4445.8     .12       0  4779.6     .05       0  4977.5     .12       0
  4995.3     .07       0  5055.6     .12       0    5222     .05       0
  5427.9     .12       0
Bank Sta=4995.3,5055.6
XS Rating Curve= 0 ,0
Exp/Cntr=0.3,0.1

Type RM Length L Ch R = 1 ,7740    ,999,999,999
BEGIN DESCRIPTION:
LITTLE LLANO RIVER 11.0
END DESCRIPTION:
XS GIS Cut Line= 3
      2850055.69     10256753.12      2849925.78     10255930.52
      2849877.18     10255631.94
#Sta/Elev= 30
  4544.6  979.16  4640.8  975.16    4678  972.18  4757.2  966.44  4770.7  967.33
  4797.7  963.41  4833.1  960.86  4868.6  955.45  4888.8  950.08  4895.5  949.48
  4939.4  947.49  4969.8  949.56    4970  946.27  4971.5  945.27  5028.8  945.27
  5030.3  946.27  5087.9  954.94    5093  954.51  5155.4  958.87  5202.7  964.22
  5217.8  964.06    5237  965.77  5293.8  970.51    5395  971.64  5409.7  973.11
    5466  973.73  5476.3  975.25  5506.5  975.52  5599.3  980.97  5679.9  981.99
#Mann= 5 ,-1 , 0
  4544.6     .12       0    4678     .05       0    4970     .05       0
  5030.3     .05       0    5237     .12       0
Bank Sta=4970,5030.3
XS Rating Curve= 0 ,0
Exp/Cntr=0.3,0.1

Type RM Length L Ch R = 1 ,6741    ,702,702,702
BEGIN DESCRIPTION:
LITTLE LLANO RIVER 10.0
END DESCRIPTION:
XS GIS Cut Line= 3
      2851259.14     10256576.39      2850821.42     10255898.34
      2850399.37     10255570.47
#Sta/Elev= 30
    4360  992.29  4393.8  995.19  4430.1  994.03  4466.4  989.68  4472.4  987.41
  4487.5  985.83  4523.8  977.56  4617.5  971.31  4720.5  967.05    4799  958.85
  4828.1  957.81  4856.4  953.56  4871.6  947.72  4892.7  944.42  4944.2  946.23
  4971.2  945.71  4986.4  944.87  5000.3  941.73  5001.8  940.73  5059.2  940.73
  5060.7  941.73  5066.2  950.95  5131.6  956.68  5166.5  956.83  5181.7  958.41
  5338.3  969.69  5431.9  972.94  5668.2  978.42  5685.1  978.77  5701.5  978.96
#Mann= 9 ,-1 , 0
    4360     .05       0  5000.3     .05       0  5060.7     .05       0
  5166.5     .12       0  5181.7     .05       0  5338.3     .12       0
  5431.9     .05       0  5668.2     .12       0  5685.1     .05       0
Bank Sta=5000.3,5060.7
XS Rating Curve= 0 ,0
Exp/Cntr=0.3,0.1

Type RM Length L Ch R = 1 ,6039    ,577,577,577
BEGIN DESCRIPTION:
LITTLE LLANO RIVER 9.0
END DESCRIPTION:
XS GIS Cut Line= 3
      2852266.06     10255854.13      2851682.73     10255527.74
      2850641.08      10255520.8
#Sta/Elev= 30
  3993.5  993.76  4192.3  987.36  4208.3  990.61    4214  989.11    4230     992
  4267.6  988.77  4273.4  986.43    4311  989.04  4316.8  987.25  4435.5  977.38
  4538.3  971.96  4597.6  971.34    4699   974.2    4745  970.75    4759  969.92
    4779  963.17  4807.2  957.44    4829  953.59    4899  953.23    4929  943.51
  4948.7  939.43  4950.2  938.43  5009.2  939.43    5019  942.19    5109     945
    5149  954.74    5259  966.23    5439  971.22    5499  969.33  5703.6  972.46
#Mann= 5 ,-1 , 0
  3993.5     .05       0    4745     .12       0  4807.2     .05       0
  4948.7     .03       0  5009.2     .05       0
Bank Sta=4948.7,5009.2
XS Rating Curve= 0 ,0
Exp/Cntr=0.3,0.1

Type RM Length L Ch R = 1 ,5462    ,449,449,449
BEGIN DESCRIPTION:
LITTLE LLANO RIVER 8.0
END DESCRIPTION:
XS GIS Cut Line= 3
      2852092.45     10254340.24      2851641.06     10254798.58
      2850559.21     10255353.37
#Sta/Elev= 30
  4003.4  977.05  4059.7  975.81  4172.9  977.49  4236.5  974.26    4293  973.19
  4314.3  974.69  4349.6  972.78    4385  973.68  4547.6   970.2  4632.5  964.17
  4690.8  962.31  4814.3  954.99  4848.6  956.62  4877.5  949.91    4900  948.94
  4907.1  945.23  4922.5  940.65  4957.1  941.02  4987.8  939.16  4989.3  938.16
  5048.3  939.16  5084.7  942.39  5113.5  947.14  5129.1  947.23  5173.5  953.64
    5190  957.55  5225.9  961.04  5417.6  966.63  5694.9   967.1  5862.5  971.51
#Mann= 5 ,-1 , 0
  4003.4     .05       0  4814.3     .12       0  4848.6     .05       0
  4987.8     .03       0  5048.3     .05       0
Bank Sta=4987.8,5048.3
XS Rating Curve= 0 ,0
Exp/Cntr=0.3,0.1

Type RM Length L Ch R = 1 ,5013    ,609,609,609
BEGIN DESCRIPTION:
LITTLE LLANO RIVER 7.0
END DESCRIPTION:
XS GIS Cut Line= 3
      2851772.98     10253881.93      2850925.78     10254763.86
      2850440.15     10255277.24
#Sta/Elev= 30
  4054.2  982.57  4081.5  980.74    4145  983.47  4244.1  982.83  4293.5  980.85
  4343.2  981.35  4442.2  977.74    4534  972.23  4625.9  969.84  4654.2  965.96
  4682.5  967.01  4755.2  962.13  4817.1  960.25  4887.8  952.18  4931.3  948.85
  4937.2   947.6  4942.2  937.22  4943.7  936.22  5002.7  937.22  5014.9  938.85
    5107  941.04  5121.2  942.52  5135.3  946.67  5170.5  949.99  5206.1  956.28
  5255.5  960.24  5545.5  963.97  5736.4  964.38  5835.5   966.8  5983.8  974.21
#Mann= 5 ,-1 , 0
  4054.2     .05       0  4755.2     .12       0  4931.3     .05       0
  4942.2     .03       0  5002.7     .05       0
Bank Sta=4942.2,5002.7
XS Rating Curve= 0 ,0
Exp/Cntr=0.3,0.1

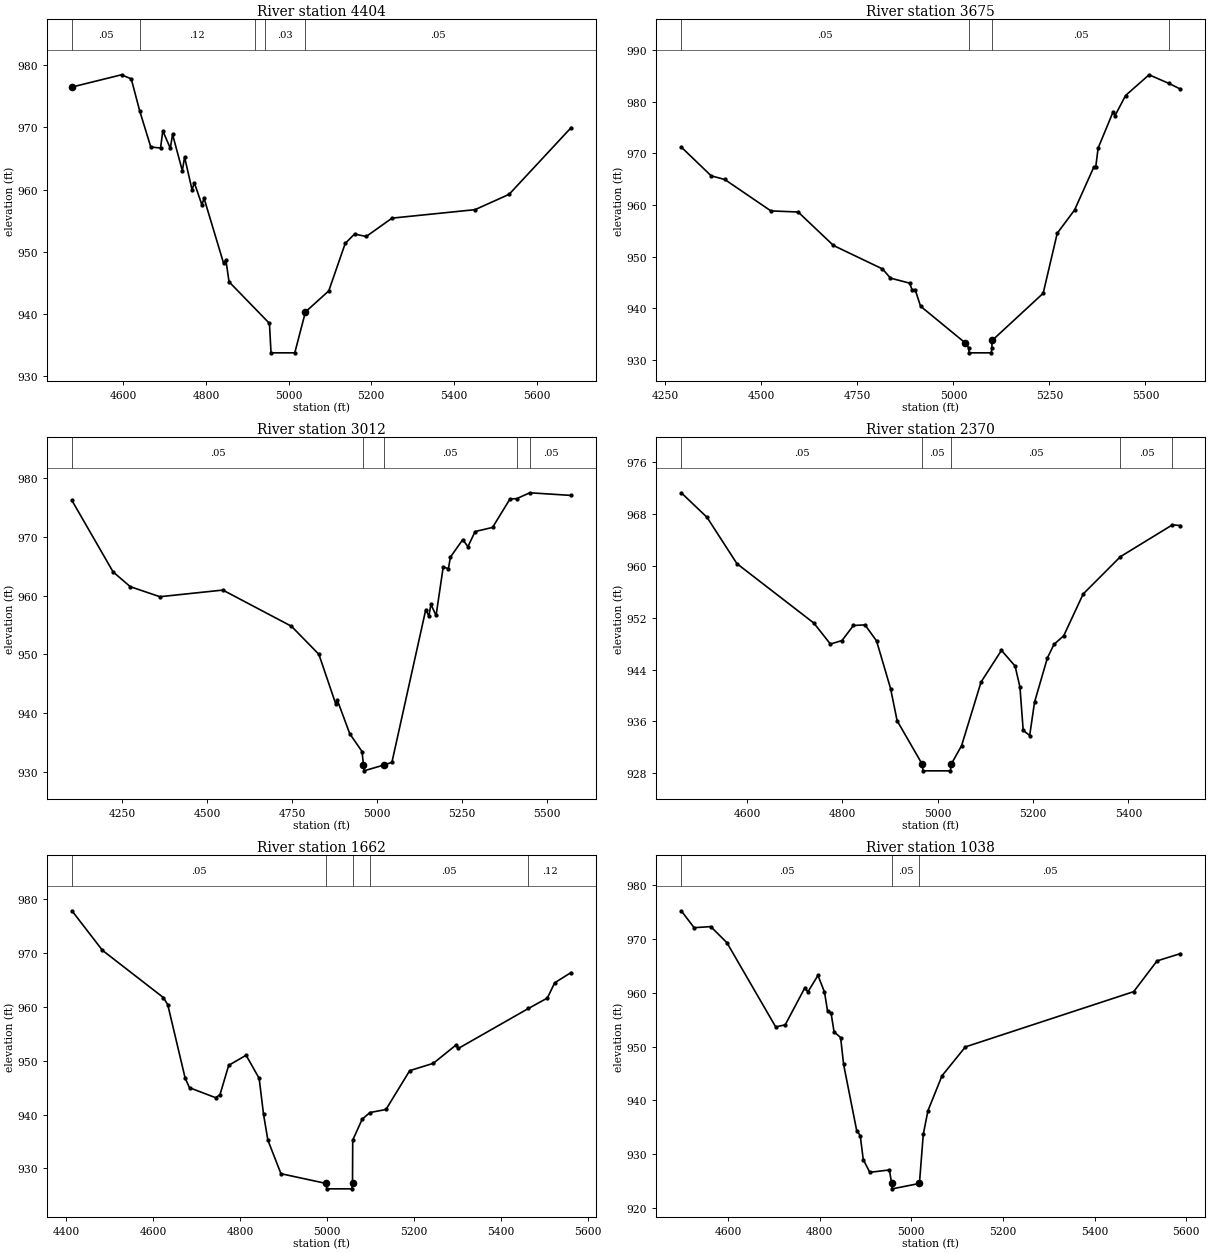
Type RM Length L Ch R = 1 ,4404    ,729,729,729
BEGIN DESCRIPTION:
LITTLE LLANO RIVER 6.0
END DESCRIPTION:
XS GIS Cut Line= 3
       2850755.7     10253903.08      2850550.25       10254386.
      2850255.69      10255003.1
#Sta/Elev= 30
  4475.2  976.49  4595.2  978.46  4618.8   977.8  4639.6  972.58  4666.1  966.86
  4689.7  966.69  4695.2  969.44  4713.4  966.66  4718.8  968.89  4742.5  963.03
  4747.9  965.24  4766.1  959.96  4771.5  961.12  4789.7  957.59  4795.2  958.59
  4842.5  948.15  4847.9  948.72  4855.6   945.2  4953.4  938.52  4957.2  933.79
  5014.7  933.79  5040.5  940.36    5097  943.74  5136.8  951.36  5159.5  952.88
  5187.7  952.48  5250.2  955.43  5451.1  956.79  5533.6  959.25  5683.8  969.97
#Mann= 5 ,-1 , 0
  4475.2     .05       0  4639.6     .12       0  4918.1     .05       0
  4942.4     .03       0  5040.5     .05       0
Bank Sta=4475.2,5040.5
XS Rating Curve= 0 ,0
Exp/Cntr=0.3,0.1

Type RM Length L Ch R = 1 ,3675    ,663,663,663
BEGIN DESCRIPTION:
LITTLE LLANO RIVER 5.0
END DESCRIPTION:
XS GIS Cut Line= 3
      2850355.71     10254003.09       2849834.5       10254483.
      2849255.73      10254603.1
#Sta/Elev= 30
  4291.5  971.21  4369.5  965.64  4404.7  964.94  4524.9  958.86  4595.8  958.65
  4687.6  952.18  4815.3  947.64  4836.2  945.86  4886.1  944.89  4892.9  943.49
  4900.3  943.65  4914.5  940.43  5029.8  933.39  5039.5  932.41    5041  931.41
  5098.6  931.41  5100.1  932.41  5100.9  933.81  5233.7  942.93  5270.3  954.54
  5315.4  959.03  5365.5  967.33  5370.6  967.34  5376.7     971  5415.7  978.01
  5420.8   977.3  5448.2  981.18  5509.4  985.19    5561  983.52  5591.1  982.42
#Mann= 4 ,-1 , 0
  4291.5     .05       0  5039.5     .03       0  5100.1     .05       0
    5561     .12       0
Bank Sta=5029.8,5100.9
XS Rating Curve= 0 ,0
Exp/Cntr=0.3,0.1

Type RM Length L Ch R = 1 ,3012    ,642,642,642
BEGIN DESCRIPTION:
LITTLE LLANO RIVER 4.0
END DESCRIPTION:
XS GIS Cut Line= 3
      2850405.68     10253953.11      2849515.75       10254074.
      2849205.68     10254553.12
#Sta/Elev= 30
  4101.9  976.16    4223  964.02  4273.5  961.51  4360.6   959.8  4545.9  960.93
  4747.8  954.78  4828.5  950.01  4877.9   941.6    4883  942.18  4919.3  936.52
  4955.5  933.48  4959.7   931.2  4961.2   930.2  5020.3   931.2  5043.4  931.65
    5143  957.61  5152.2  956.51  5158.2   958.5  5173.3  956.61  5194.4  964.88
  5209.6  964.56  5215.5  966.53  5251.8  969.51    5267  968.31  5288.1  970.88
  5339.5  971.58    5391  976.44  5410.1  976.46  5449.1  977.47  5570.7  977.02
#Mann= 5 ,-1 , 0
  4101.9     .05       0  4959.7     .03       0  5020.3     .05       0
  5410.1     .12       0  5449.1     .05       0
Bank Sta=4959.7,5020.3
XS Rating Curve= 0 ,0
Exp/Cntr=0.3,0.1

Type RM Length L Ch R = 1 ,2370    ,708,708,708
BEGIN DESCRIPTION:
LITTLE LLANO RIVER 3.0
END DESCRIPTION:
XS GIS Cut Line= 3
      2850405.71     10253803.12       2849906.5       10253602.
      2849805.68     10253103.09
#Sta/Elev= 30
  4461.8  971.23  4515.7  967.46  4578.6  960.31  4739.8  951.17  4774.7  947.93
  4798.9  948.47    4823  950.79  4847.2  950.88  4871.4  948.43  4900.9  941.07
  4914.6  936.12  4967.4   929.4  4968.9   928.4  5026.5   928.4    5028   929.4
  5049.9  932.29  5090.7  942.08  5133.5  946.96  5162.1  944.54  5172.3  941.29
  5179.1  934.64  5192.7  933.84  5202.9  938.98  5229.9   945.8  5243.7  947.88
  5264.1   949.2  5304.9  955.64  5383.1  961.39  5492.1  966.29    5509  966.18
#Mann= 5 ,-1 , 0
  4461.8     .05       0  4967.4     .05       0    5028     .05       0
  5383.1     .05       0  5492.1     .12       0
Bank Sta=4967.4,5028
XS Rating Curve= 0 ,0
Exp/Cntr=0.3,0.1

Type RM Length L Ch R = 1 ,1662    ,624,624,624
BEGIN DESCRIPTION:
LITTLE LLANO RIVER 2.0
END DESCRIPTION:
XS GIS Cut Line= 3
      2851055.72     10253153.11      2850469.75       10253178.
      2849955.69     10252953.11
#Sta/Elev= 30
  4413.5  977.84  4483.6   970.5  4623.7  961.73  4633.7  960.42  4673.8  946.76
  4683.8  944.99  4743.8  943.14  4753.8  943.69  4773.9  949.15  4813.9  951.02
  4843.9  946.73  4853.9  940.09  4863.9  935.28    4894  929.03  4997.8  927.22
  4999.3  926.22    5057  926.22  5058.5  927.22    5059  935.26  5080.8  939.16
  5098.8  940.39  5135.4  940.95    5190  948.16  5244.2  949.52  5296.4  952.91
  5301.9  952.29  5462.8   959.7  5506.5  961.64  5523.3  964.47  5561.1  966.38
#Mann= 5 ,-1 , 0
  4413.5     .05       0  4997.8     .05       0  5058.5     .05       0
  5098.8     .05       0  5462.8     .12       0
Bank Sta=4997.8,5058.5
XS Rating Curve= 0 ,0
Exp/Cntr=0.3,0.1

Type RM Length L Ch R = 1 ,1038    ,0,0,0
BEGIN DESCRIPTION:
LITTLE LLANO RIVER 1.0
END DESCRIPTION:
XS GIS Cut Line= 3
      2851055.71     10253053.14       2850731.5       10252670.
      2850155.64      10252553.1
#Sta/Elev= 30
  4498.1  975.23  4526.1  972.09  4562.4  972.29  4597.6  969.32  4704.2  953.66
    4725  954.05  4767.9  960.94  4774.4  960.15  4796.4  963.23  4810.7  960.14
  4817.3  956.64    4825  956.25  4831.6  952.75  4845.9  951.68  4852.4   946.7
    4881   934.4  4888.7  933.47  4895.3  929.02  4909.6  926.66  4952.4   927.1
  4957.2  924.59  4958.7  923.59  5017.9  924.59  5026.3  933.73  5036.5   938.1
  5067.2  944.59  5118.2  949.95  5485.5  960.21  5536.5  965.92  5587.6  967.28
#Mann= 3 ,-1 , 0
  4498.1     .05       0  4957.2     .05       0  5017.9     .05       0
Bank Sta=4957.2,5017.9
XS Rating Curve= 0 ,0
Exp/Cntr=0.3,0.1
Stream Node=LITTLE LLANO RIV,Reach-1         , 0 , 0 ,Upstream end
Stream Node=LITTLE LLANO RIV,Reach-1         , 0 , 1 ,Downstream end

Chan Stop Cuts=-1
Use User Specified Reach Order=0
Composite Channel Slope=5