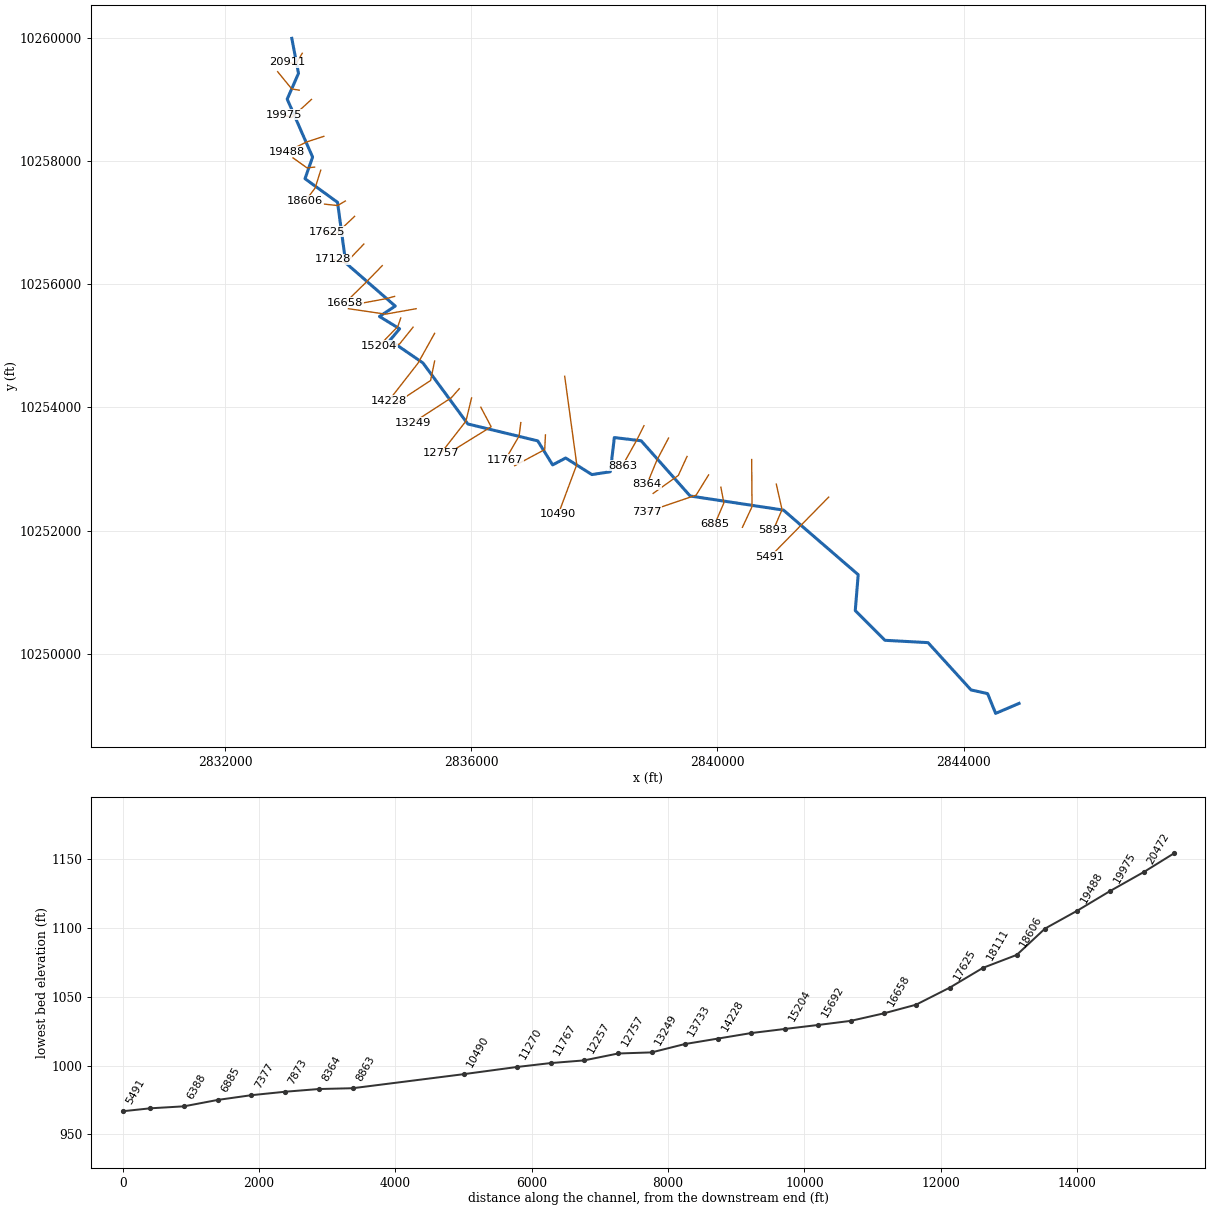
--- LITTLE SANDY CREEK.prj (project) ---

Proj Title=LITTLE SANDY CREEK Base Level Engineering
Current Plan=p01
Default Exp/Contr=0.3,0.1
English Units
Geom File=g01
Flow File=f01
Plan File=p01
BEGIN DESCRIPTION:
LITTLE SANDY CREEK
END DESCRIPTION:

--- LITTLE SANDY CREEK.p01 (plan) ---

Plan Title=Multiple Run
Short Identifier=Multiple
Geom File=g01
Flow File=f01
Subcritical Flow
K Sum by GR= 0
Std Step Tol= 0.01
Critical Tol= 0.01
Num of Std Step Trials= 20
Max Error Tol= 0.3
Flow Tol Ratio= 0.001
Split Flow NTrial= 30
Split Flow Tol= 0.02
Split Flow Ratio= 0.02
Log Output Level= 0
Friction Slope Method= 1
Unsteady Friction Slope Method= 2
Unsteady Bridges Friction Slope Method= 1
Parabolic Critical Depth
Global Vel Dist=  1 , 1 , 1
Global Log Level= 0
CheckData=True
Encroach Param= -1, 0, 0, 0
BEGIN DESCRIPTION:
Multiple Run
END DESCRIPTION:

--- LITTLE SANDY CREEK.f01 (steady flow) ---

Flow Title=Multiple
Number of Profiles=7
Profile Names=10-year,25-year,50-year,1pct_min,100-year,1pct_plu,500-year
River Rch & RM= LITTLE SANDY CRE,Reach-1,20911
     536     877    1581    1240    2193    3880    3110
River Rch & RM= LITTLE SANDY CRE,Reach-1,10490
     783    1315    2284    1709    3190    5955    4488
River Rch & RM= LITTLE SANDY CRE,Reach-1,6388
     984    1676    2911    2144    4091    7805    5732
River Rch & RM= LITTLE SANDY CRE,Reach-1,3439
    1194    2063    3572    2577    5049    9892    7065
Boundary for River Rch & Prof#=LITTLE SANDY CRE,Reach-1,1
Up Type=0
Dn Type=3
Dn Slope=0.005
Boundary for River Rch & Prof#=LITTLE SANDY CRE,Reach-1,2
Up Type=0
Dn Type=3
Dn Slope=0.005
Boundary for River Rch & Prof#=LITTLE SANDY CRE,Reach-1,3
Up Type=0
Dn Type=3
Dn Slope=0.005
Boundary for River Rch & Prof#=LITTLE SANDY CRE,Reach-1,4
Up Type=0
Dn Type=3
Dn Slope=0.005
Boundary for River Rch & Prof#=LITTLE SANDY CRE,Reach-1,5
Up Type=0
Dn Type=3
Dn Slope=0.005
Boundary for River Rch & Prof#=LITTLE SANDY CRE,Reach-1,6
Up Type=0
Dn Type=3
Dn Slope=0.005
Boundary for River Rch & Prof#=LITTLE SANDY CRE,Reach-1,7
Up Type=0
Dn Type=3
Dn Slope=0.005

--- LITTLE SANDY CREEK.g01 (geometry) ---

Geom Title=Existing Conditions

River Reach=LITTLE SANDY CRE,Reach-1
Reach XY= 30
      2833085.50     10259995.00      2833194.75     10259426.00
      2833011.00     10259008.00      2833423.50     10258066.00
      2833300.25     10257715.00      2833828.50     10257331.00
      2833962.25     10256346.00      2834765.75     10255646.00
      2834509.75     10255477.00      2834836.50     10255277.00
      2834679.75     10255090.00      2835216.00     10254722.00
      2835944.75     10253731.00      2837081.25     10253456.00
      2837322.25     10253066.00      2837534.25     10253178.00
      2837959.50     10252909.00      2838259.25     10252955.00
      2838324.75     10253510.00      2838760.25     10253458.00
      2839556.00     10252561.00      2841071.75     10252332.00
      2842286.00     10251283.00      2842238.25     10250700.00
      2842719.50     10250217.00      2843420.25     10250179.00
      2844118.50     10249411.00      2844387.75     10249351.00
      2844518.25     10249030.00      2844899.00     10249192.00

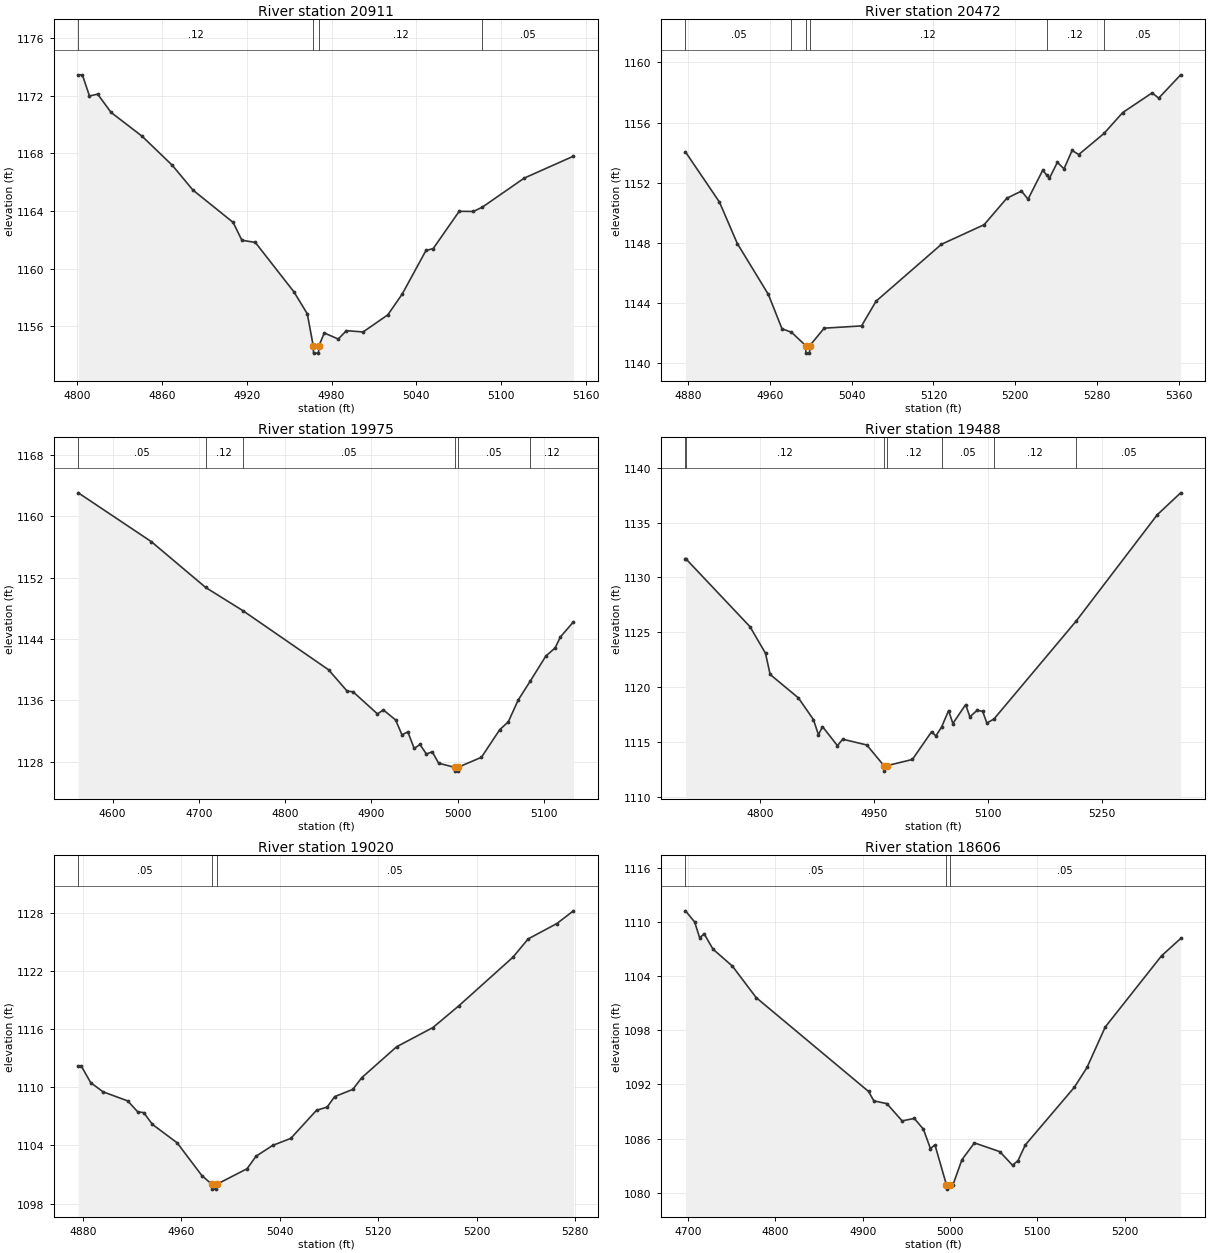
Type RM Length L Ch R = 1,20911,439,439,439
BEGIN DESCRIPTION:
LITTLE SANDY CREEK 41.0
END DESCRIPTION:
XS GIS Cut Line= 3
      2833255.70     10259753.14      2833155.25     10259581.00
      2833005.68     10259603.11
#Sta/Elev= 30
  4800.7 1173.46  4803.6 1173.46  4808.6 1171.99  4814.4 1172.12  4823.9 1170.85
  4845.8 1169.20  4867.3 1167.17  4881.8 1165.46  4910.3 1163.21  4916.5 1161.97
  4926.0 1161.82  4953.3 1158.39  4962.8 1156.86  4967.0 1154.63  4967.2 1154.13
  4970.7 1154.13  4971.0 1154.63  4974.8 1155.53  4984.7 1155.11  4990.5 1155.69
  5002.3 1155.60  5019.8 1156.79  5029.9 1158.22  5046.8 1161.26  5051.9 1161.39
  5070.3 1163.98  5080.4 1163.97  5086.7 1164.27  5116.4 1166.29  5151.2 1167.81
#Mann=4,-1,0
  4800.7    0.12       0  4967.0    0.07       0  4971.0    0.12       0
  5086.7    0.05       0
Bank Sta=4967,4971
Exp/Cntr=0.3,0.1

Type RM Length L Ch R = 1,20472,497,497,497
BEGIN DESCRIPTION:
LITTLE SANDY CREEK 40.0
END DESCRIPTION:
XS GIS Cut Line= 3
      2833205.72     10259153.10      2833084.75     10259173.00
      2832855.71     10259453.07
#Sta/Elev= 30
  4877.4 1154.05  4910.6 1150.72  4928.1 1147.96  4958.5 1144.57  4971.8 1142.29
  4981.1 1142.06  4995.0 1141.17  4995.2 1140.67  4998.7 1140.67  4999.0 1141.17
  5013.1 1142.33  5049.6 1142.48  5063.9 1144.13  5127.8 1147.91  5169.5 1149.21
  5191.7 1150.97  5206.1 1151.45  5212.5 1150.91  5226.9 1152.84  5230.6 1152.53
  5233.4 1152.30  5241.2 1153.36  5247.7 1152.93  5255.6 1154.15  5262.1 1153.88
  5286.8 1155.28  5305.1 1156.67  5333.9 1157.98  5340.3 1157.63  5361.8 1159.18
#Mann=6,-1,0
  4877.4    0.05       0  4981.1    0.12       0  4995.0    0.03       0
  4999.0    0.12       0  5230.6    0.12       0  5286.8    0.05       0
Bank Sta=4995,4999
Exp/Cntr=0.3,0.1

Type RM Length L Ch R = 1,19975,487,487,487
BEGIN DESCRIPTION:
LITTLE SANDY CREEK 39.0
END DESCRIPTION:
XS GIS Cut Line= 3
      2833405.66     10259003.09      2833081.50     10258706.00
      2832955.73     10258753.10
#Sta/Elev= 30
  4560.3 1163.03  4645.0 1156.67  4707.9 1150.71  4750.9 1147.70  4850.4 1139.99
  4872.0 1137.20  4878.7 1137.13  4907.1 1134.24  4913.9 1134.76  4928.1 1133.46
  4935.5 1131.52  4942.3 1131.90  4949.7 1129.74  4956.4 1130.26  4963.8 1129.02
  4970.6 1129.31  4978.0 1127.82  4996.4 1127.29  4996.7 1126.79  5000.2 1126.79
  5000.4 1127.29  5027.6 1128.59  5048.9 1132.20  5058.7 1133.20  5070.3 1136.06
  5084.3 1138.53  5102.3 1141.78  5113.0 1142.83  5119.2 1144.27  5134.3 1146.23
#Mann=6,-1,0
  4560.3    0.05       0  4707.9    0.12       0  4750.9    0.05       0
  4996.4    0.05       0  5000.4    0.05       0  5084.3    0.12       0
Bank Sta=4996.4,5000.4
Exp/Cntr=0.3,0.1

Type RM Length L Ch R = 1,19488,468,468,468
BEGIN DESCRIPTION:
LITTLE SANDY CREEK 38.0
END DESCRIPTION:
XS GIS Cut Line= 3
      2833605.71     10258403.12      2833322.00     10258310.00
      2833005.67     10258153.11
#Sta/Elev= 30
  4701.4 1131.72  4701.6 1131.72  4786.2 1125.52  4806.7 1123.09  4812.8 1121.16
  4849.9 1119.03  4869.8 1117.05  4876.4 1115.66  4881.7 1116.41  4901.4 1114.67
  4908.3 1115.26  4940.1 1114.73  4962.5 1112.85  4962.8 1112.35  4966.5 1112.85
  5000.0 1113.41  5025.3 1115.94  5030.9 1115.56  5038.4 1116.36  5047.7 1117.87
  5053.3 1116.69  5070.1 1118.41  5075.7 1117.30  5085.2 1117.89  5092.5 1117.80
  5098.1 1116.73  5107.5 1117.11  5215.4 1126.01  5322.3 1135.71  5353.1 1137.71
#Mann=7,-1,0
  4701.4    0.05       0  4701.6    0.12       0  4962.5    0.07       0
  4966.5    0.12       0  5038.4    0.05       0  5107.5    0.12       0
  5215.4    0.05       0
Bank Sta=4962.5,4966.5
Exp/Cntr=0.3,0.1

Type RM Length L Ch R = 1,19020,414,414,414
BEGIN DESCRIPTION:
LITTLE SANDY CREEK 37.0
END DESCRIPTION:
XS GIS Cut Line= 3
      2833455.71     10257903.11      2833332.50     10257891.00
      2833105.68     10258053.12
#Sta/Elev= 30
  4876.2 1112.17  4878.7 1112.17  4886.3 1110.47  4896.3 1109.53  4916.4 1108.59
  4924.4 1107.48  4929.4 1107.38  4936.5 1106.17  4956.6 1104.27  4976.7 1100.89
  4984.8 1100.00  4985.0 1099.50  4988.5 1099.50  4988.8 1100.00  5013.4 1101.60
  5020.7 1102.89  5034.3 1104.01  5049.0 1104.73  5069.9 1107.63  5078.5 1107.95
  5084.6 1109.03  5099.4 1109.78  5106.7 1110.99  5135.0 1114.17  5164.5 1116.15
  5185.4 1118.37  5229.6 1123.40  5241.9 1125.28  5265.3 1126.87  5278.8 1128.18
#Mann=3,-1,0
  4876.2    0.05       0  4984.8    0.03       0  4988.8    0.05       0
Bank Sta=4984.8,4988.8
Exp/Cntr=0.3,0.1

Type RM Length L Ch R = 1,18606,495,495,495
BEGIN DESCRIPTION:
LITTLE SANDY CREEK 36.0
END DESCRIPTION:
XS GIS Cut Line= 3
      2833555.69     10257853.14      2833464.75     10257564.00
      2833305.65     10257353.07
#Sta/Elev= 30
  4696.9 1111.27  4707.4 1110.03  4713.1 1108.29  4718.4 1108.70  4728.4 1107.02
  4750.7 1105.13  4777.9 1101.64  4906.6 1091.23  4912.7 1090.18  4927.6 1089.88
  4945.1 1087.96  4959.0 1088.24  4969.5 1087.04  4977.5 1084.89  4982.7 1085.30
  4995.8 1080.89  4996.1 1080.39  4999.8 1080.89  5003.4 1080.89  5013.6 1083.65
  5027.9 1085.52  5057.0 1084.55  5071.6 1083.04  5077.9 1083.56  5086.2 1085.29
  5142.4 1091.69  5156.9 1093.89  5177.8 1098.38  5242.3 1106.28  5264.2 1108.20
#Mann=3,-1,0
  4696.9    0.05       0  4995.8    0.05       0  4999.8    0.05       0
Bank Sta=4995.8,4999.8
Exp/Cntr=0.3,0.1

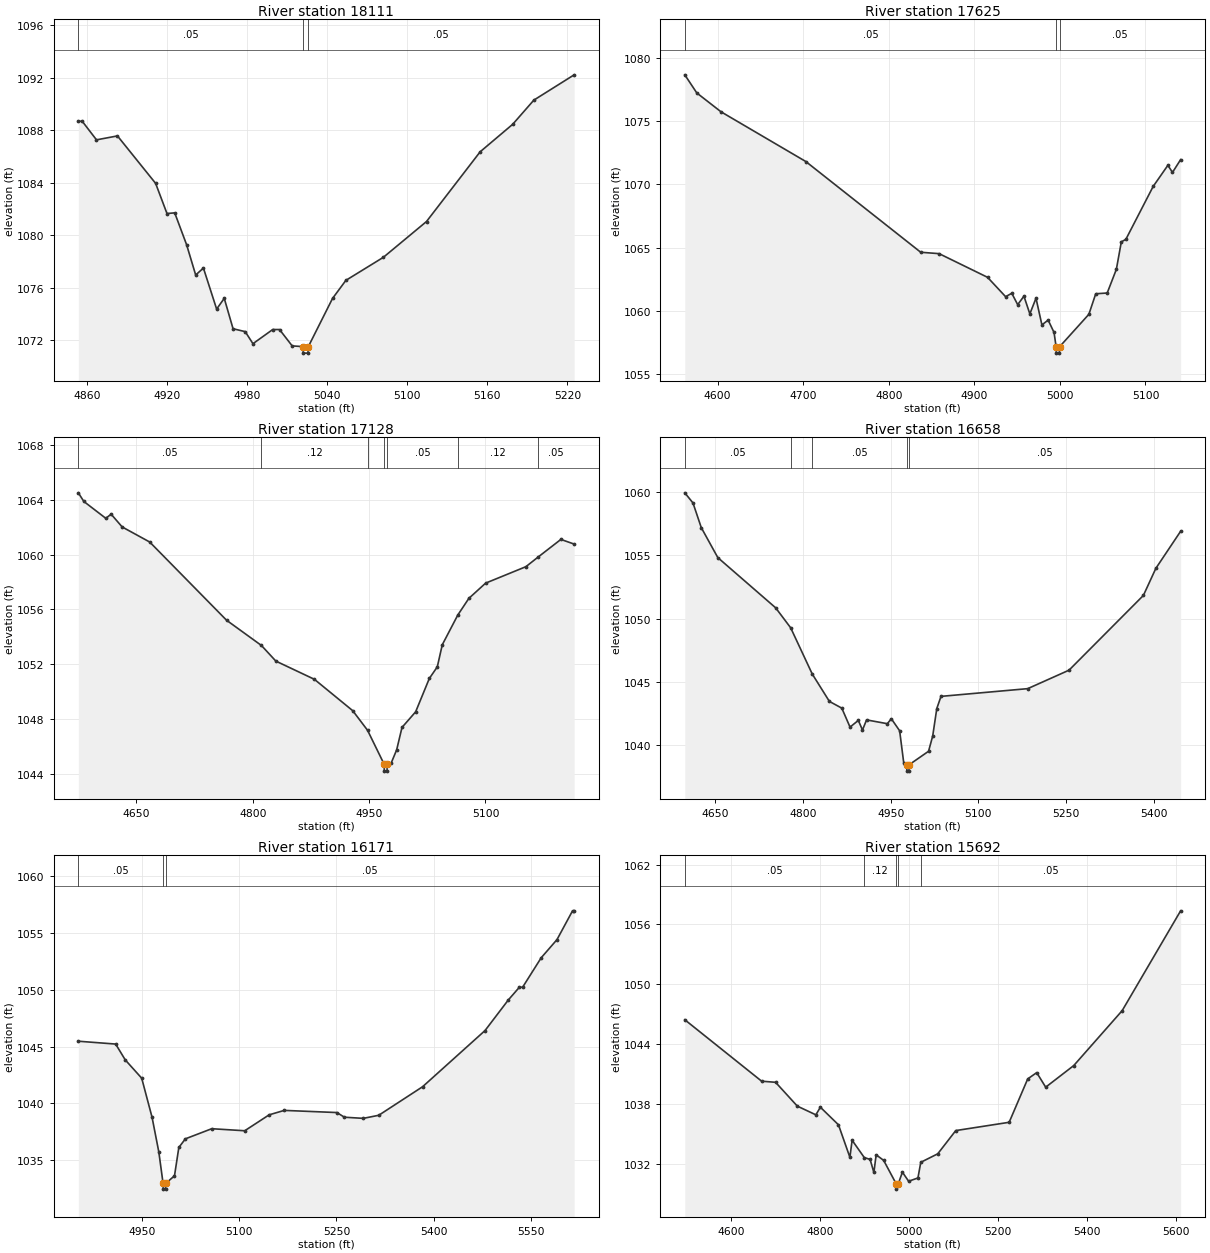
Type RM Length L Ch R = 1,18111,486,486,486
BEGIN DESCRIPTION:
LITTLE SANDY CREEK 35.0
END DESCRIPTION:
XS GIS Cut Line= 3
      2833955.65     10257353.09      2833829.50     10257279.00
      2833605.69     10257303.11
#Sta/Elev= 30
  4853.7 1088.69  4856.6 1088.69  4867.3 1087.27  4883.0 1087.57  4911.6 1083.95
  4920.1 1081.65  4925.9 1081.70  4934.8 1079.27  4941.6 1076.96  4947.4 1077.49
  4957.3 1074.36  4963.0 1075.18  4969.6 1072.86  4978.7 1072.64  4984.5 1071.72
  4999.3 1072.80  5004.4 1072.80  5013.9 1071.55  5022.0 1071.50  5022.2 1071.00
  5025.7 1071.00  5026.0 1071.50  5044.1 1075.17  5054.1 1076.55  5082.2 1078.31
  5114.5 1081.04  5154.7 1086.36  5179.1 1088.46  5194.9 1090.30  5225.1 1092.23
#Mann=3,-1,0
  4853.7    0.05       0  5022.0    0.05       0  5026.0    0.05       0
Bank Sta=5022,5026
Exp/Cntr=0.3,0.1

Type RM Length L Ch R = 1,17625,497,497,497
BEGIN DESCRIPTION:
LITTLE SANDY CREEK 34.0
END DESCRIPTION:
XS GIS Cut Line= 3
      2834105.72     10257103.14      2833787.25     10256802.00
      2833655.73     10256853.10
#Sta/Elev= 30
  4561.7 1078.66  4575.7 1077.23  4604.0 1075.74  4703.1 1071.81  4837.4 1064.64
  4858.9 1064.53  4915.5 1062.66  4936.6 1061.13  4943.8 1061.40  4950.7 1060.50
  4958.0 1061.17  4964.9 1059.77  4972.1 1061.01  4979.0 1058.90  4986.3 1059.28
  4993.2 1058.30  4995.6 1057.17  4995.9 1056.67  4999.4 1056.67  4999.6 1057.17
  5033.9 1059.74  5041.9 1061.36  5055.3 1061.42  5066.0 1063.29  5071.8 1065.46
  5077.1 1065.66  5109.0 1069.84  5126.2 1071.51  5131.6 1070.95  5141.1 1071.96
#Mann=3,-1,0
  4561.7    0.05       0  4995.6    0.03       0  4999.6    0.05       0
Bank Sta=4995.6,4999.6
Exp/Cntr=0.3,0.1

Type RM Length L Ch R = 1,17128,470,470,470
BEGIN DESCRIPTION:
LITTLE SANDY CREEK 33.0
END DESCRIPTION:
XS GIS Cut Line= 3
      2834255.71     10256653.14      2833962.25     10256346.00
      2833755.70     10256403.11
#Sta/Elev= 30
  4575.2 1064.51  4582.3 1063.88  4610.6 1062.65  4617.5 1062.95  4631.7 1062.02
  4667.2 1060.92  4766.3 1055.21  4811.2 1053.37  4829.8 1052.23  4879.5 1050.90
  4928.9 1048.61  4948.0 1047.18  4969.4 1044.70  4969.6 1044.20  4973.1 1044.20
  4973.4 1044.70  4978.3 1044.77  4985.5 1045.75  4992.4 1047.39  5010.0 1048.53
  5027.6 1050.96  5037.9 1051.81  5044.3 1053.42  5064.3 1055.59  5078.6 1056.81
  5100.2 1057.92  5152.1 1059.12  5168.0 1059.83  5197.2 1061.11  5214.3 1060.77
#Mann=7,-1,0
  4575.2    0.05       0  4811.2    0.12       0  4948.0    0.05       0
  4969.4    0.03       0  4973.4    0.05       0  5064.3    0.12       0
  5168.0    0.05       0
Bank Sta=4969.4,4973.4
Exp/Cntr=0.3,0.1

Type RM Length L Ch R = 1,16658,487,487,487
BEGIN DESCRIPTION:
LITTLE SANDY CREEK 32.0
END DESCRIPTION:
XS GIS Cut Line= 3
      2834555.68     10256303.11      2834274.75     10256015.00
      2833955.67     10255703.10
#Sta/Elev= 30
  4597.6 1059.94  4611.6 1059.14  4625.8 1057.19  4654.1 1054.82  4753.1 1050.85
  4778.8 1049.27  4815.7 1045.62  4845.1 1043.45  4866.3 1042.92  4880.4 1041.42
  4894.6 1041.95  4901.7 1041.19  4908.7 1041.99  4944.2 1041.69  4951.1 1042.08
  4965.3 1041.13  4972.4 1038.56  4977.4 1038.44  4977.7 1037.94  4981.2 1037.94
  4981.4 1038.44  5014.8 1039.51  5021.9 1040.72  5028.9 1042.89  5036.1 1043.85
  5184.5 1044.46  5255.2 1045.92  5382.5 1051.83  5403.8 1053.97  5446.2 1056.90
#Mann=5,-1,0
  4597.6    0.05       0  4778.8    0.12       0  4815.7    0.05       0
  4977.4    0.05       0  4981.4    0.05       0
Bank Sta=4977.4,4981.4
Exp/Cntr=0.3,0.1

Type RM Length L Ch R = 1,16171,479,479,479
BEGIN DESCRIPTION:
LITTLE SANDY CREEK 31.0
END DESCRIPTION:
XS GIS Cut Line= 3
      2834755.67     10255803.11      2834612.25     10255765.00
      2834005.68     10255653.11
#Sta/Elev= 30
  4851.6 1045.47  4909.2 1045.22  4924.0 1043.83  4949.4 1042.22  4965.4 1038.78
  4975.8 1035.74  4982.4 1032.97  4982.7 1032.47  4986.2 1032.47  4986.4 1032.97
  5000.0 1033.64  5006.7 1036.13  5016.8 1036.89  5057.5 1037.78  5108.4 1037.60
  5146.1 1039.00  5169.4 1039.39  5250.7 1039.20  5262.2 1038.79  5291.4 1038.69
  5315.2 1038.96  5382.9 1041.47  5479.3 1046.41  5515.1 1049.09  5532.2 1050.21
  5537.3 1050.22  5566.0 1052.81  5590.3 1054.40  5614.3 1056.93  5616.8 1056.93
#Mann=3,-1,0
  4851.6    0.05       0  4982.4    0.03       0  4986.4    0.05       0
Bank Sta=4982.4,4986.4
Exp/Cntr=0.3,0.1

Type RM Length L Ch R = 1,15692,488,488,488
BEGIN DESCRIPTION:
LITTLE SANDY CREEK 30.0
END DESCRIPTION:
XS GIS Cut Line= 3
      2835105.68     10255603.11      2834610.25     10255515.00
      2834005.64     10255603.12
#Sta/Elev= 30
  4496.8 1046.45  4669.5 1040.29  4700.8 1040.18  4749.7 1037.79  4791.3 1036.92
  4801.5 1037.68  4842.1 1035.92  4867.8 1032.66  4872.8 1034.37  4900.2 1032.63
  4913.2 1032.45  4921.7 1031.14  4926.8 1032.91  4943.7 1032.35  4972.2 1029.97
  4972.4 1029.47  4976.2 1029.97  4985.8 1031.17  4999.8 1030.26  5020.7 1030.59
  5027.1 1032.16  5065.2 1033.01  5105.7 1035.34  5225.7 1036.17  5267.4 1040.52
  5287.6 1041.15  5307.8 1039.69  5370.9 1041.86  5479.6 1047.36  5611.0 1057.37
#Mann=5,-1,0
  4496.8    0.05       0  4900.2    0.12       0  4972.2    0.07       0
  4976.2    0.12       0  5027.1    0.05       0
Bank Sta=4972.2,4976.2
Exp/Cntr=0.3,0.1

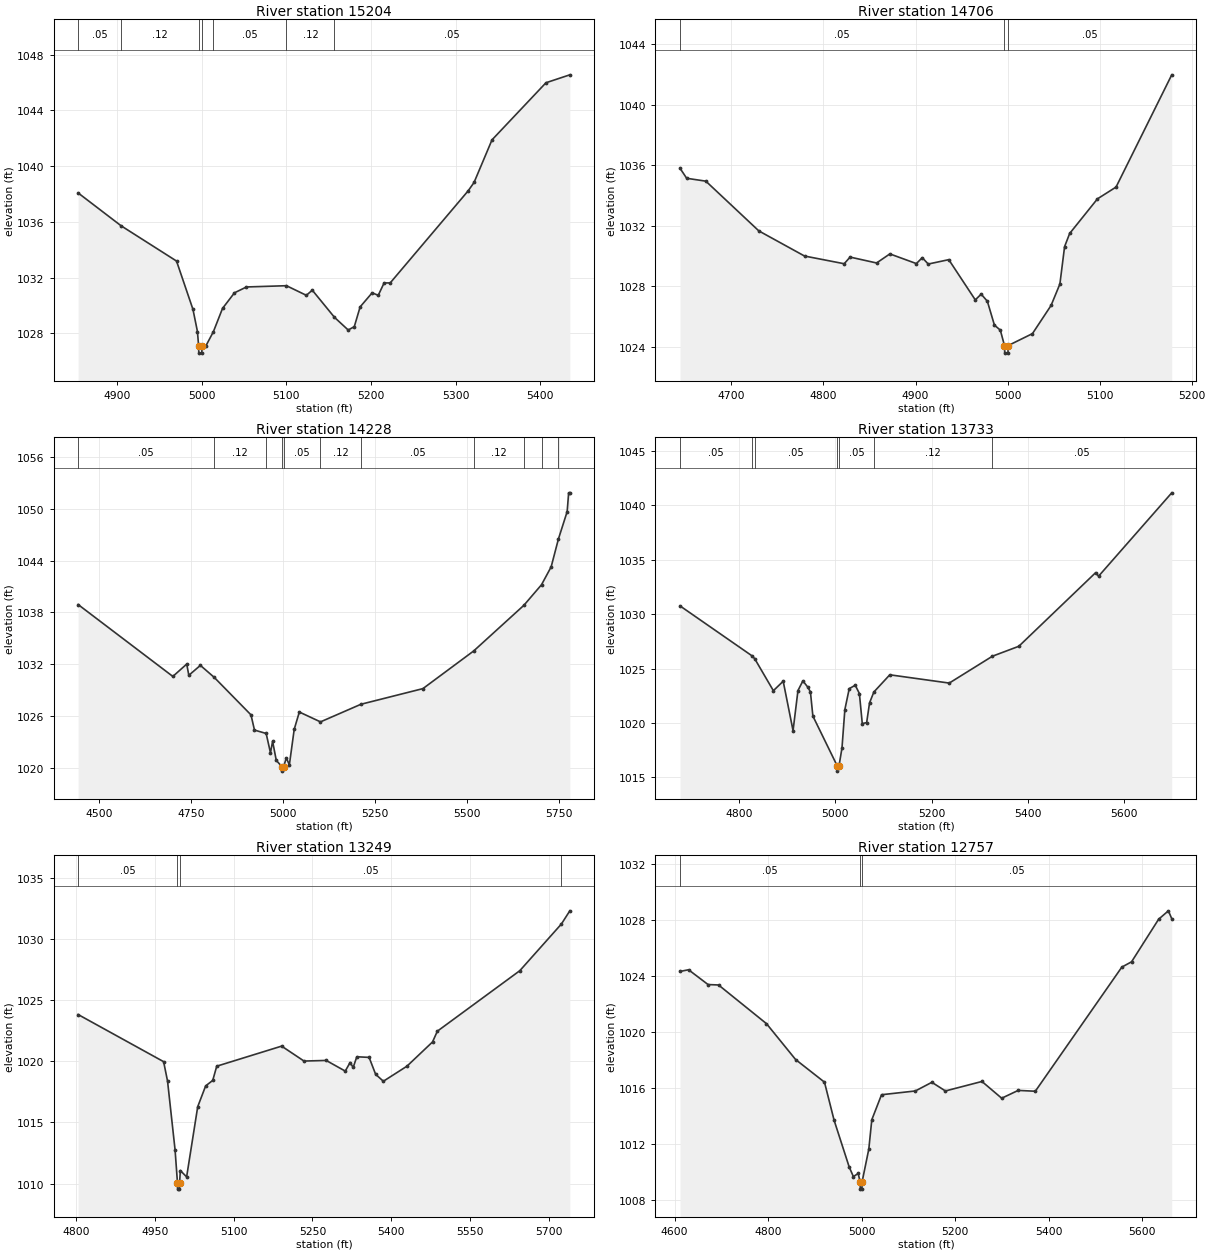
Type RM Length L Ch R = 1,15204,498,498,498
BEGIN DESCRIPTION:
LITTLE SANDY CREEK 29.0
END DESCRIPTION:
XS GIS Cut Line= 3
      2834855.67     10255453.07      2834808.50     10255315.00
      2834505.69     10255003.12
#Sta/Elev= 30
  4854.1 1038.08  4904.9 1035.72  4970.3 1033.19  4989.7 1029.72  4995.0 1028.13
  4996.4 1027.08  4996.6 1026.58  5000.1 1026.58  5000.4 1027.08  5004.8 1027.08
  5013.9 1028.13  5024.6 1029.79  5038.7 1030.91  5052.9 1031.33  5100.1 1031.42
  5123.6 1030.73  5130.6 1031.10  5156.8 1029.15  5173.0 1028.24  5180.2 1028.48
  5187.1 1029.90  5201.3 1030.91  5208.5 1030.73  5215.4 1031.62  5222.6 1031.62
  5314.5 1038.22  5321.6 1038.83  5342.8 1041.89  5406.5 1045.99  5434.7 1046.56
#Mann=7,-1,0
  4854.1    0.05       0  4904.9    0.12       0  4996.4    0.07       0
  5000.4    0.12       0  5013.9    0.05       0  5100.1    0.12       0
  5156.8    0.05       0
Bank Sta=4996.4,5000.4
Exp/Cntr=0.3,0.1

Type RM Length L Ch R = 1,14706,478,478,478
BEGIN DESCRIPTION:
LITTLE SANDY CREEK 28.0
END DESCRIPTION:
XS GIS Cut Line= 3
      2835055.68     10255303.10      2834832.50     10255026.00
      2834655.68     10255003.11
#Sta/Elev= 30
  4644.2 1035.79  4651.4 1035.13  4672.2 1034.94  4729.8 1031.65  4779.4 1029.99
  4822.5 1029.48  4828.9 1029.92  4857.7 1029.53  4872.1 1030.13  4900.9 1029.49
  4907.3 1029.88  4913.8 1029.46  4936.1 1029.75  4964.9 1027.09  4971.3 1027.47
  4978.0 1027.00  4985.7 1025.42  4992.1 1025.09  4996.6 1024.07  4996.9 1023.57
  5000.4 1023.57  5000.6 1024.07  5027.0 1024.86  5047.2 1026.72  5056.8 1028.14
  5061.9 1030.61  5067.4 1031.48  5097.6 1033.77  5117.8 1034.55  5178.3 1041.97
#Mann=3,-1,0
  4644.2    0.05       0  4996.6    0.05       0  5000.6    0.05       0
Bank Sta=4996.6,5000.6
Exp/Cntr=0.3,0.1

Type RM Length L Ch R = 1,14228,495,495,495
BEGIN DESCRIPTION:
LITTLE SANDY CREEK 27.0
END DESCRIPTION:
XS GIS Cut Line= 3
      2835405.68     10255203.10      2835134.75     10254717.00
      2834655.68     10254103.11
#Sta/Elev= 30
  4443.5 1038.92  4700.7 1030.60  4738.4 1032.03  4744.1 1030.73  4775.5 1031.88
  4813.1 1030.49  4912.9 1026.15  4922.4 1024.39  4954.1 1024.00  4965.8 1021.76
  4971.6 1023.09  4981.6 1020.88  4997.4 1020.14  4997.6 1019.64  5001.4 1020.14
  5008.9 1021.18  5017.1 1020.36  5030.3 1024.48  5044.2 1026.48  5101.6 1025.34
  5211.6 1027.38  5379.8 1029.19  5517.7 1033.55  5653.9 1038.83  5701.8 1041.21
  5728.0 1043.28  5747.7 1046.50  5771.5 1049.68  5775.5 1051.85  5778.7 1051.85
#Mann=11,-1,0
  4443.5    0.05       0  4813.1    0.12       0  4954.1    0.05       0
  4997.4    0.05       0  5001.4    0.05       0  5101.6    0.12       0
  5211.6    0.05       0  5517.7    0.12       0  5653.9    0.05       0
  5701.8    0.12       0  5747.7    0.05       0
Bank Sta=4997.4,5001.4
Exp/Cntr=0.3,0.1

Type RM Length L Ch R = 1,13733,484,484,484
BEGIN DESCRIPTION:
LITTLE SANDY CREEK 26.0
END DESCRIPTION:
XS GIS Cut Line= 3
      2835405.68     10254753.10      2835340.25     10254437.00
      2834755.72     10254053.14
#Sta/Elev= 30
  4677.2 1030.76  4827.2 1026.16  4832.5 1025.90  4871.2 1022.97  4891.6 1023.84
  4912.1 1019.30  4922.3 1022.98  4932.5 1023.87  4942.7 1023.30  4948.2 1022.86
  4953.3 1020.64  5003.7 1016.08  5004.0 1015.58  5007.7 1016.08  5013.8 1017.70
  5019.8 1021.24  5028.9 1023.16  5041.4 1023.47  5050.0 1022.71  5056.0 1019.95
  5065.1 1020.04  5071.1 1021.85  5080.1 1022.85  5113.2 1024.43  5236.8 1023.67
  5326.6 1026.14  5381.4 1027.05  5541.2 1033.82  5547.2 1033.49  5699.3 1041.15
#Mann=7,-1,0
  4677.2    0.05       0  4827.2    0.12       0  4832.5    0.05       0
  5003.7    0.03       0  5007.7    0.05       0  5080.1    0.12       0
  5326.6    0.05       0
Bank Sta=5003.7,5007.7
Exp/Cntr=0.3,0.1

Type RM Length L Ch R = 1,13249,492,492,492
BEGIN DESCRIPTION:
LITTLE SANDY CREEK 25.0
END DESCRIPTION:
XS GIS Cut Line= 3
      2835805.65     10254303.08      2835676.25     10254156.00
      2835055.67     10253753.10
#Sta/Elev= 30
  4804.1 1023.81  4966.8 1019.96  4974.3 1018.37  4988.6 1012.76  4993.2 1010.05
  4993.5 1009.55  4997.0 1009.55  4997.2 1010.05  4998.6 1011.07  5010.6 1010.55
  5031.7 1016.28  5046.8 1017.98  5060.3 1018.43  5067.9 1019.59  5191.4 1021.23
  5234.0 1020.01  5276.2 1020.06  5312.5 1019.19  5321.7 1019.89  5327.6 1019.49
  5334.5 1020.36  5357.9 1020.31  5370.3 1018.93  5385.0 1018.36  5429.9 1019.59
  5478.6 1021.57  5487.8 1022.45  5644.7 1027.39  5723.8 1031.20  5739.9 1032.28
#Mann=4,-1,0
  4804.1    0.05       0  4993.2    0.05       0  4997.2    0.05       0
  5723.8    0.12       0
Bank Sta=4993.2,4997.2
Exp/Cntr=0.3,0.1

Type RM Length L Ch R = 1,12757,500,500,500
BEGIN DESCRIPTION:
LITTLE SANDY CREEK 24.0
END DESCRIPTION:
XS GIS Cut Line= 3
      2836005.68     10254153.10      2835913.50     10253776.00
      2835505.70     10253253.13
#Sta/Elev= 30
  4611.8 1024.34  4630.0 1024.46  4671.7 1023.40  4694.1 1023.37  4796.6 1020.60
  4858.9 1018.03  4920.6 1016.41  4941.2 1013.68  4973.5 1010.33  4982.4 1009.65
  4992.7 1009.87  4996.9 1009.25  4997.2 1008.75  5000.7 1008.75  5000.9 1009.25
  5015.4 1011.62  5021.8 1013.72  5042.6 1015.51  5114.9 1015.78  5150.2 1016.40
  5179.2 1015.78  5257.3 1016.46  5299.5 1015.26  5334.8 1015.82  5371.4 1015.76
  5556.4 1024.65  5577.2 1025.03  5635.1 1028.08  5655.9 1028.68  5663.1 1028.12
#Mann=3,-1,0
  4611.8    0.05       0  4996.9    0.05       0  5000.9    0.05       0
Bank Sta=4996.9,5000.9
Exp/Cntr=0.3,0.1

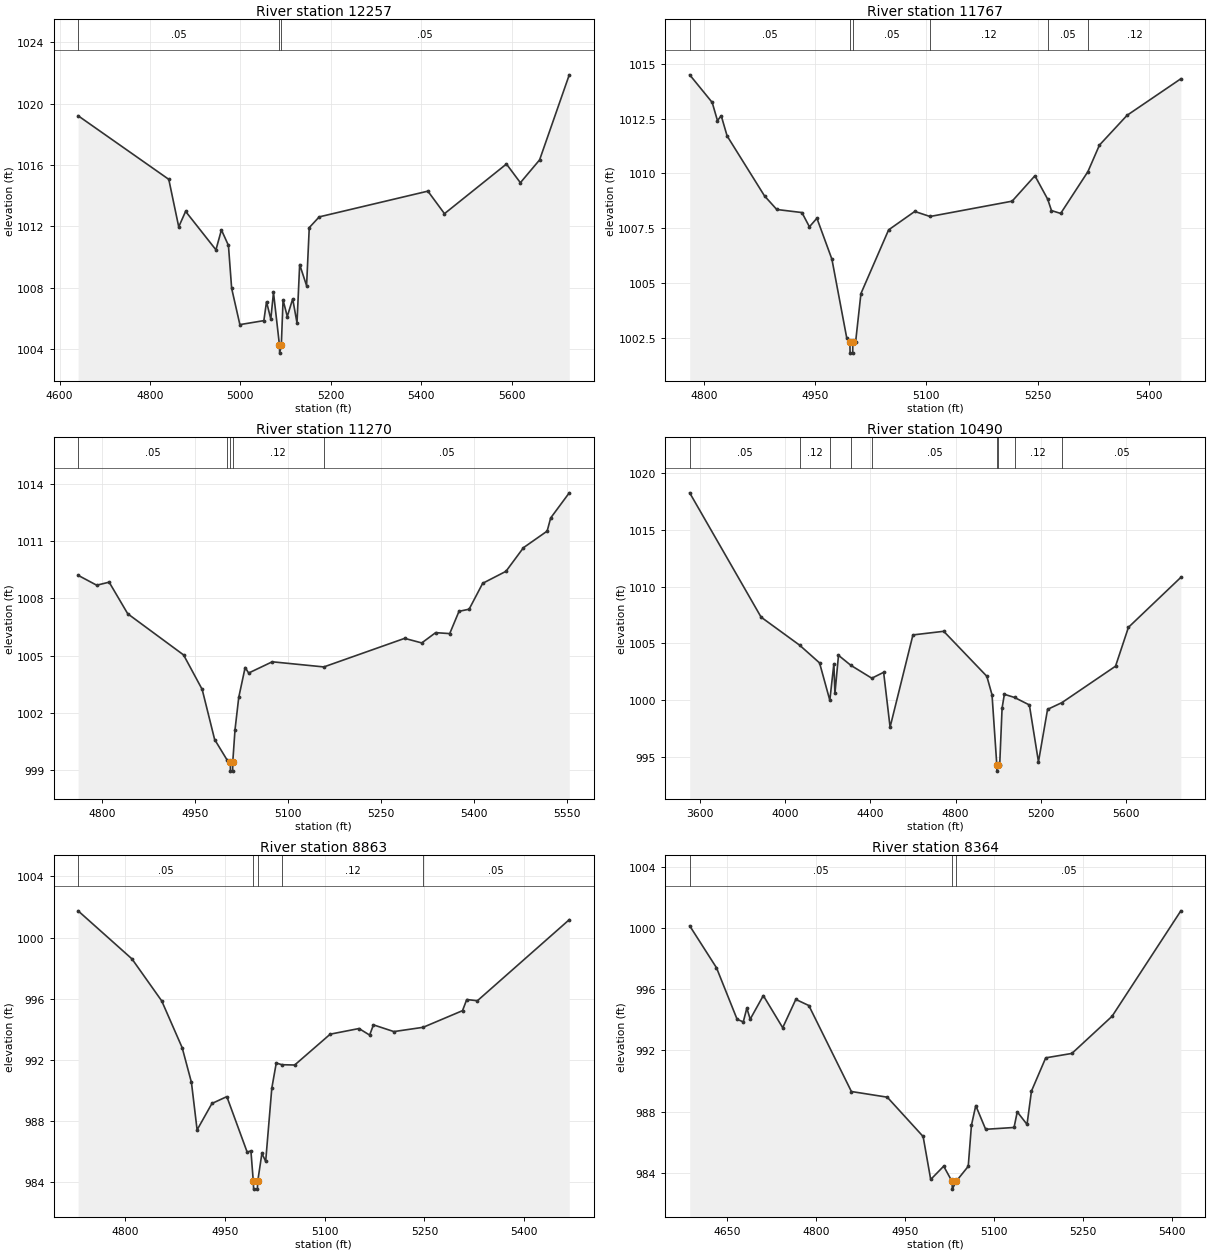
Type RM Length L Ch R = 1,12257,490,490,490
BEGIN DESCRIPTION:
LITTLE SANDY CREEK 23.0
END DESCRIPTION:
XS GIS Cut Line= 3
      2836155.68     10254003.12      2836323.75     10253686.00
      2835705.65     10253303.09
#Sta/Elev= 30
  4641.1 1019.22  4841.6 1015.07  4863.6 1011.97  4878.8 1012.98  4945.9 1010.47
  4958.0 1011.77  4973.5 1010.76  4980.6 1007.96  4998.8 1005.59  5051.8 1005.85
  5057.7 1007.08  5067.2 1005.95  5073.1 1007.69  5086.4 1004.23  5086.7 1003.73
  5090.4 1004.23  5094.3 1007.20  5103.6 1006.12  5115.6 1007.27  5125.1 1005.70
  5131.0 1009.51  5146.3 1008.13  5152.2 1011.92  5174.2 1012.62  5414.5 1014.30
  5451.2 1012.83  5588.2 1016.07  5619.0 1014.85  5661.5 1016.34  5727.1 1021.89
#Mann=3,-1,0
  4641.1    0.05       0  5086.4    0.05       0  5090.4    0.05       0
Bank Sta=5086.4,5090.4
Exp/Cntr=0.3,0.1

Type RM Length L Ch R = 1,11767,497,497,497
BEGIN DESCRIPTION:
LITTLE SANDY CREEK 22.0
END DESCRIPTION:
XS GIS Cut Line= 3
      2836805.69     10253753.14      2836778.00     10253536.00
      2836555.66     10253153.07
#Sta/Elev= 30
  4781.1 1014.50  4811.4 1013.24  4818.5 1012.41  4823.6 1012.63  4831.5 1011.71
  4881.9 1008.97  4898.4 1008.35  4932.3 1008.21  4942.4 1007.56  4952.5 1007.95
  4972.7 1006.08  4992.8 1002.46  4996.9 1002.29  4997.2 1001.79  5000.7 1001.79
  5000.9 1002.29  5004.6 1002.29  5011.8 1004.51  5049.1 1007.42  5084.3 1008.26
  5104.9 1008.03  5215.5 1008.73  5246.2 1009.89  5263.4 1008.82  5268.5 1008.30
  5280.9 1008.17  5317.6 1010.08  5333.1 1011.29  5370.3 1012.65  5442.8 1014.32
#Mann=6,-1,0
  4781.1    0.05       0  4996.9    0.05       0  5000.9    0.05       0
  5104.9    0.12       0  5263.4    0.05       0  5317.6    0.12       0
Bank Sta=4996.9,5000.9
Exp/Cntr=0.3,0.1

Type RM Length L Ch R = 1,11270,780,780,780
BEGIN DESCRIPTION:
LITTLE SANDY CREEK 21.0
END DESCRIPTION:
XS GIS Cut Line= 3
      2837205.68     10253553.11      2837194.00     10253315.00
      2836705.69     10253053.12
#Sta/Elev= 30
  4761.6 1009.21  4791.6 1008.69  4811.7 1008.85  4841.7 1007.19  4931.8 1005.03
  4961.8 1003.22  4981.9 1000.59  5001.9  999.52  5007.2  999.43  5007.4  998.93
  5010.9  998.93  5011.2  999.43  5014.8 1001.11  5020.8 1002.80  5031.1 1004.37
  5036.8 1004.08  5074.9 1004.67  5158.1 1004.40  5288.5 1005.90  5316.1 1005.66
  5338.5 1006.20  5361.2 1006.15  5376.2 1007.32  5392.5 1007.43  5414.4 1008.79
  5452.0 1009.42  5480.2 1010.66  5518.4 1011.53  5524.1 1012.22  5554.1 1013.54
#Mann=5,-1,0
  4761.6    0.05       0  5001.9    0.12       0  5007.2    0.05       0
  5011.2    0.12       0  5158.1    0.05       0
Bank Sta=5007.2,5011.2
Exp/Cntr=0.3,0.1

Type RM Length L Ch R = 1,10490,1627,1627,1627
BEGIN DESCRIPTION:
LITTLE SANDY CREEK 20.0
END DESCRIPTION:
XS GIS Cut Line= 3
      2837518.51     10254505.25      2837714.75     10253070.00
      2837414.80     10252266.88
#Sta/Elev= 30
  3551.4 1018.28  3886.6 1007.31  4067.2 1004.84  4161.1 1003.27  4209.3  999.97
  4228.3 1003.20  4233.3 1000.58  4250.0 1003.94  4307.8 1003.06  4406.4 1001.92
  4461.9 1002.44  4492.2  997.60  4599.5 1005.74  4744.0 1006.06  4946.4 1002.09
  4970.8 1000.45  4993.4  994.22  4993.8  993.72  4998.4  994.22  5006.8  994.27
  5018.0  999.28  5028.7 1000.50  5076.5 1000.22  5146.1  999.56  5188.8  994.54
  5231.5  999.17  5299.3  999.77  5550.6 1002.98  5611.2 1006.41  5857.3 1010.82
#Mann=9,-1,0
  3551.4    0.05       0  4067.2    0.12       0  4209.3    0.05       0
  4307.8    0.12       0  4406.4    0.05       0  4993.4    0.05       0
  4998.4    0.05       0  5076.5    0.12       0  5299.3    0.05       0
Bank Sta=4993.4,4998.4
Exp/Cntr=0.3,0.1

Type RM Length L Ch R = 1,8863,499,499,499
BEGIN DESCRIPTION:
LITTLE SANDY CREEK 18.0
END DESCRIPTION:
XS GIS Cut Line= 3
      2838805.66     10253703.07      2838684.50     10253461.00
      2838455.68     10253053.10
#Sta/Elev= 30
  4729.3 1001.75  4810.3  998.60  4855.0  995.85  4885.8  992.78  4899.7  990.51
  4908.2  987.40  4930.5  989.13  4952.9  989.58  4983.5  985.94  4989.1  986.03
  4992.7  984.02  4993.2  983.52  4998.8  983.52  4999.3  984.02  5005.6  985.86
  5011.3  985.34  5020.5  990.13  5027.2  991.78  5035.7  991.67  5054.9  991.65
  5108.3  993.67  5151.6  994.04  5167.6  993.61  5173.3  994.28  5204.0  993.84
  5248.0  994.12  5307.2  995.21  5313.6  995.94  5329.6  995.86  5467.7 1001.17
#Mann=5,-1,0
  4729.3    0.05       0  4992.7    0.05       0  4999.3    0.05       0
  5035.7    0.12       0  5248.0    0.05       0
Bank Sta=4992.7,4999.3
Exp/Cntr=0.3,0.1

Type RM Length L Ch R = 1,8364,491,491,491
BEGIN DESCRIPTION:
LITTLE SANDY CREEK 17.0
END DESCRIPTION:
XS GIS Cut Line= 3
      2839205.69     10253503.12      2839013.50     10253137.00
      2838855.67     10252753.08
#Sta/Elev= 30
  4586.5 1000.14  4631.7  997.40  4666.5  994.03  4676.9  993.86  4682.9  994.76
  4688.6  994.04  4710.7  995.58  4743.4  993.48  4765.5  995.33  4787.5  994.93
  4859.3  989.31  4919.8  988.94  4980.3  986.37  4993.1  983.56  5015.0  984.43
  5029.1  983.43  5029.6  982.93  5035.8  983.43  5056.4  984.42  5061.8  987.10
  5069.1  988.39  5085.8  986.84  5133.7  986.96  5139.1  987.98  5155.6  987.16
  5163.1  989.34  5187.1  991.51  5231.3  991.80  5299.1  994.23  5415.1 1001.12
#Mann=3,-1,0
  4586.5    0.05       0  5029.1    0.05       0  5035.8    0.05       0
Bank Sta=5029.1,5035.8
Exp/Cntr=0.3,0.1

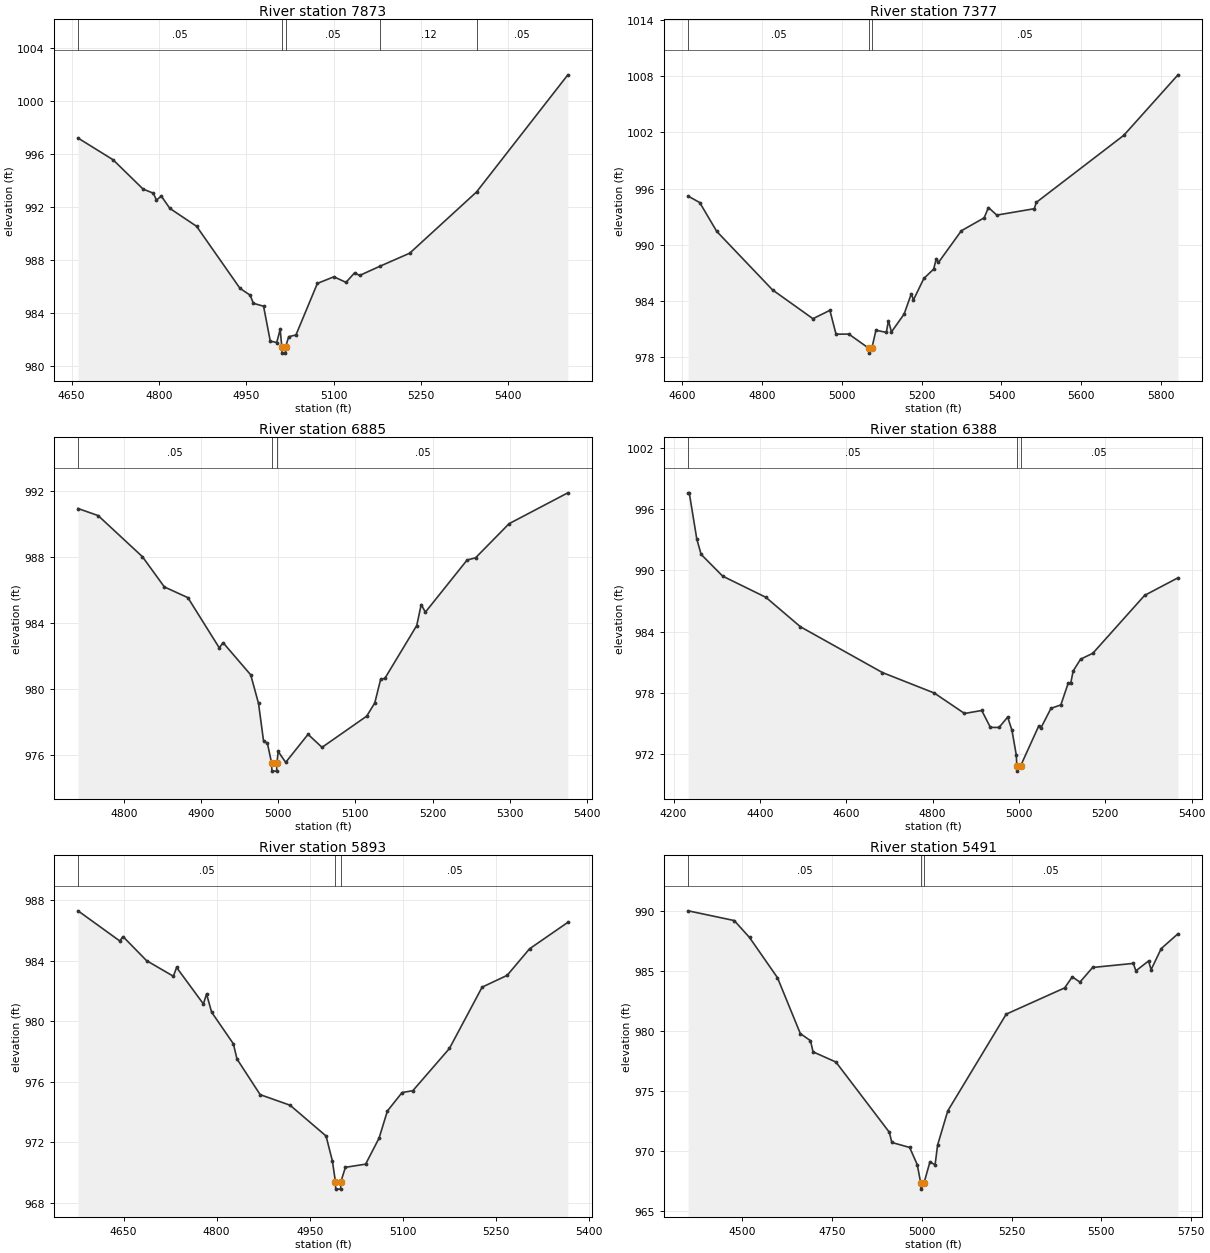
Type RM Length L Ch R = 1,7873,496,496,496
BEGIN DESCRIPTION:
LITTLE SANDY CREEK 16.0
END DESCRIPTION:
XS GIS Cut Line= 3
      2839505.67     10253203.09      2839364.25     10252895.00
      2838955.70     10252603.12
#Sta/Elev= 30
  4661.0  997.20  4721.2  995.56  4772.7  993.35  4790.2  993.04  4795.7  992.52
  4804.0  992.82  4818.7  991.89  4864.6  990.54  4939.1  985.86  4956.6  985.34
  4962.1  984.73  4979.6  984.51  4991.1  981.88  5002.2  981.77  5008.1  982.76
  5010.9  981.47  5011.4  980.97  5017.1  980.97  5017.6  981.47  5022.8  982.21
  5035.2  982.34  5072.0  986.23  5100.3  986.73  5121.2  986.31  5135.9  987.03
  5144.5  986.83  5180.1  987.54  5230.5  988.51  5345.3  993.13  5502.1 1001.97
#Mann=5,-1,0
  4661.0    0.05       0  5010.9    0.03       0  5017.6    0.05       0
  5180.1    0.12       0  5345.3    0.05       0
Bank Sta=5010.9,5017.6
Exp/Cntr=0.3,0.1

Type RM Length L Ch R = 1,7377,492,492,492
BEGIN DESCRIPTION:
LITTLE SANDY CREEK 15.0
END DESCRIPTION:
XS GIS Cut Line= 3
      2839855.67     10252903.08      2839653.25     10252575.00
      2838855.72     10252303.12
#Sta/Elev= 30
  4614.5  995.19  4643.4  994.51  4686.0  991.44  4826.0  985.20  4927.3  982.13
  4969.8  983.02  4985.2  980.48  5017.3  980.49  5067.9  978.96  5068.4  978.46
  5074.9  978.96  5085.3  980.90  5111.3  980.67  5116.6  981.91  5124.2  980.72
  5155.9  982.62  5174.0  984.79  5179.3  984.13  5205.4  986.42  5229.9  987.41
  5236.7  988.53  5242.0  988.12  5299.4  991.50  5356.6  992.88  5367.4  993.98
  5388.2  993.17  5482.2  993.85  5487.5  994.53  5706.9 1001.68  5842.6 1008.12
#Mann=3,-1,0
  4614.5    0.05       0  5067.9    0.05       0  5074.9    0.05       0
Bank Sta=5067.9,5074.9
Exp/Cntr=0.3,0.1

Type RM Length L Ch R = 1,6885,497,497,497
BEGIN DESCRIPTION:
LITTLE SANDY CREEK 14.0
END DESCRIPTION:
XS GIS Cut Line= 3
      2840055.69     10252703.07      2840104.00     10252448.00
      2839955.69     10252103.14
#Sta/Elev= 30
  4740.4  990.94  4766.5  990.51  4823.9  988.02  4852.3  986.19  4882.8  985.54
  4923.5  982.50  4928.5  982.81  4964.3  980.86  4974.4  979.13  4980.9  976.86
  4985.9  976.72  4991.3  975.53  4991.8  975.03  4997.8  975.03  4998.3  975.53
  4999.9  976.22  5009.6  975.56  5038.6  977.26  5056.7  976.47  5114.6  978.36
  5125.1  979.16  5132.7  980.59  5138.2  980.65  5179.5  983.85  5185.3  985.12
  5190.7  984.66  5244.8  987.82  5255.7  987.95  5299.2  990.02  5375.4  991.89
#Mann=3,-1,0
  4740.4    0.05       0  4991.3    0.05       0  4998.3    0.05       0
Bank Sta=4991.3,4998.3
Exp/Cntr=0.3,0.1

Type RM Length L Ch R = 1,6388,495,495,495
BEGIN DESCRIPTION:
LITTLE SANDY CREEK 13.0
END DESCRIPTION:
XS GIS Cut Line= 3
      2840555.68     10253153.08      2840561.25     10252387.00
      2840405.66     10252053.07
#Sta/Elev= 30
  4233.9  997.59  4236.4  997.59  4253.9  993.06  4263.9  991.57  4313.9  989.44
  4413.9  987.37  4493.9  984.49  4683.9  980.01  4803.9  978.01  4873.9  976.01
  4913.9  976.30  4933.9  974.65  4953.9  974.64  4973.9  975.66  4983.9  974.35
  4993.9  971.94  4995.1  970.87  4995.6  970.37  5003.7  970.87  5045.8  974.78
  5051.3  974.63  5074.2  976.51  5097.1  976.85  5114.4  979.01  5119.9  978.95
  5125.6  980.17  5142.8  981.32  5171.2  981.90  5291.1  987.56  5368.4  989.28
#Mann=3,-1,0
  4233.9    0.05       0  4995.1    0.05       0  5003.7    0.05       0
Bank Sta=4995.1,5003.7
Exp/Cntr=0.3,0.1

Type RM Length L Ch R = 1,5893,402,402,402
BEGIN DESCRIPTION:
LITTLE SANDY CREEK 12.0
END DESCRIPTION:
XS GIS Cut Line= 3
      2840955.69     10252753.09      2841049.00     10252340.00
      2840905.69     10252003.12
#Sta/Elev= 30
  4576.5  987.30  4643.8  985.31  4649.0  985.60  4687.0  984.01  4730.2  982.98
  4735.4  983.56  4778.6  981.15  4783.7  981.81  4791.8  980.61  4826.9  978.52
  4832.8  977.51  4870.1  975.16  4918.4  974.46  4976.3  972.43  4986.6  970.77
  4991.4  969.42  4991.9  968.92  4999.8  968.92  5000.3  969.42  5007.5  970.36
  5040.1  970.57  5061.8  972.29  5075.2  974.08  5098.9  975.30  5116.2  975.42
  5175.2  978.21  5227.9  982.26  5268.3  983.04  5304.3  984.79  5366.1  986.54
#Mann=3,-1,0
  4576.5    0.05       0  4991.4    0.05       0  5000.3    0.05       0
Bank Sta=4991.4,5000.3
Exp/Cntr=0.3,0.1

Type RM Length L Ch R = 1,5491,913,913,913
BEGIN DESCRIPTION:
Mapping XS 2e0538f9
END DESCRIPTION:
XS GIS Cut Line= 2
      2841806.68     10252543.40      2840851.82     10251571.19
#Sta/Elev= 30
  4350.4  989.99  4478.5  989.18  4521.0  987.77  4598.8  984.42  4662.4  979.76
  4690.7  979.17  4697.8  978.24  4761.4  977.39  4910.0  971.54  4917.0  970.69
  4966.6  970.27  4987.7  968.84  4997.4  967.30  4997.9  966.80  5006.3  967.30
  5023.1  969.08  5037.3  968.82  5044.3  970.47  5072.6  973.32  5235.2  981.38
  5397.9  983.57  5419.0  984.49  5440.3  984.05  5475.6  985.27  5588.8  985.61
  5595.9  984.99  5631.2  985.81  5638.3  985.09  5666.6  986.85  5713.1  988.08
#Mann=3,-1,0
  4350.4    0.05       0  4997.4    0.05       0  5006.3    0.05       0
Bank Sta=4997.4,5006.3
Exp/Cntr=0.3,0.1