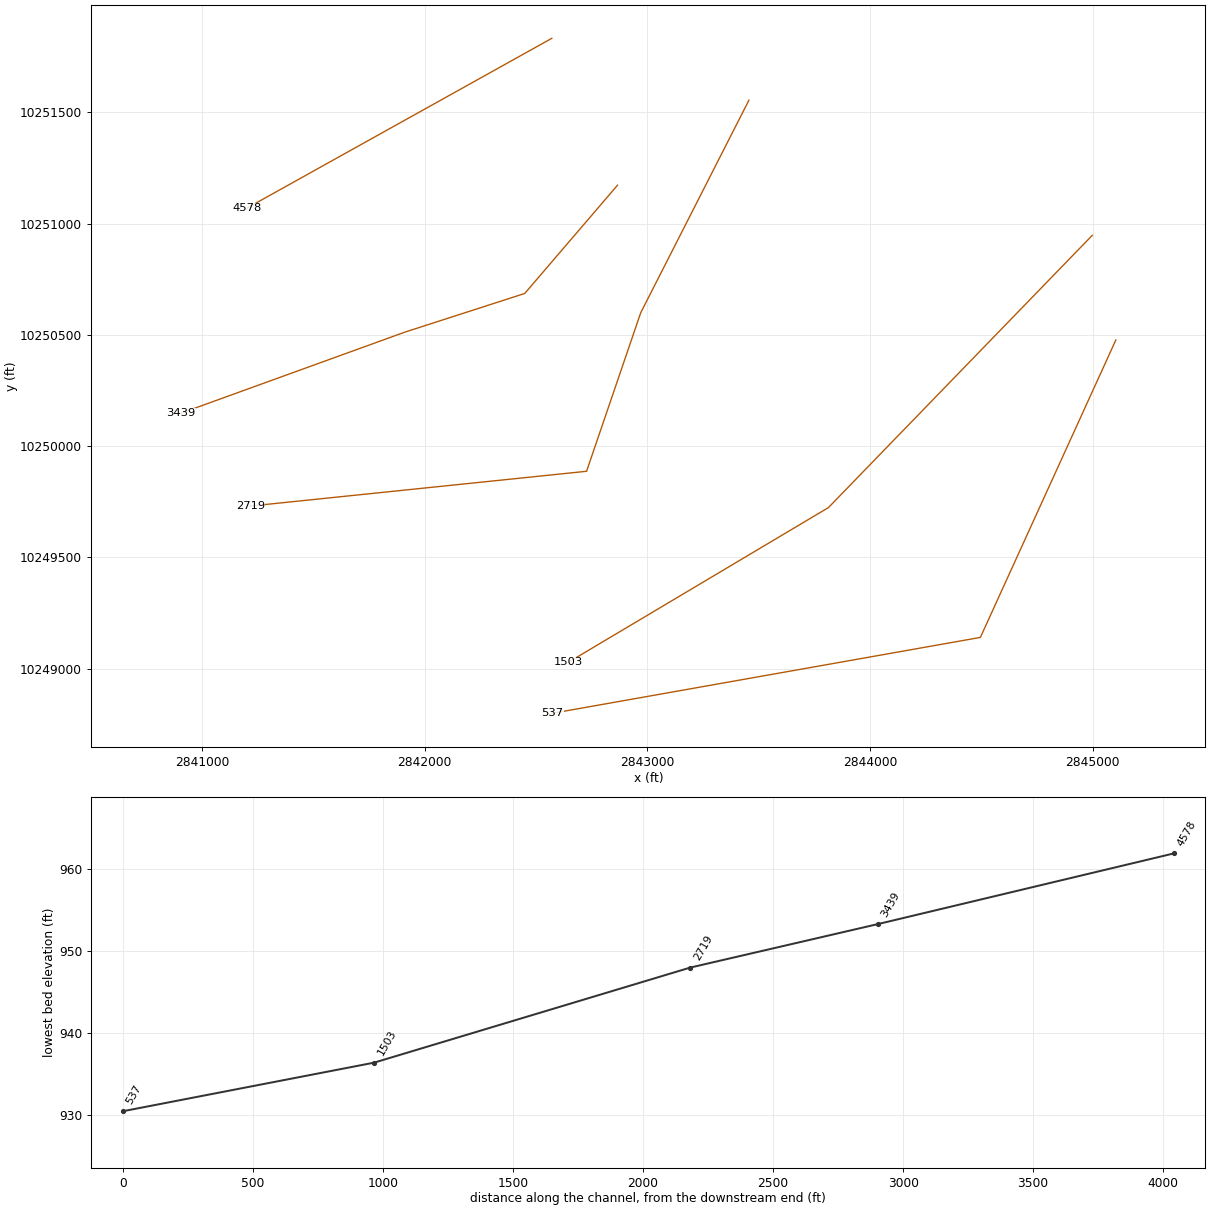
HEC-RAS study LITTLE SANDY CREEK.prj: LITTLE SANDY CREEK Base Level Engineering

--- LITTLE SANDY CREEK.g01 (geometry) --- (continued)

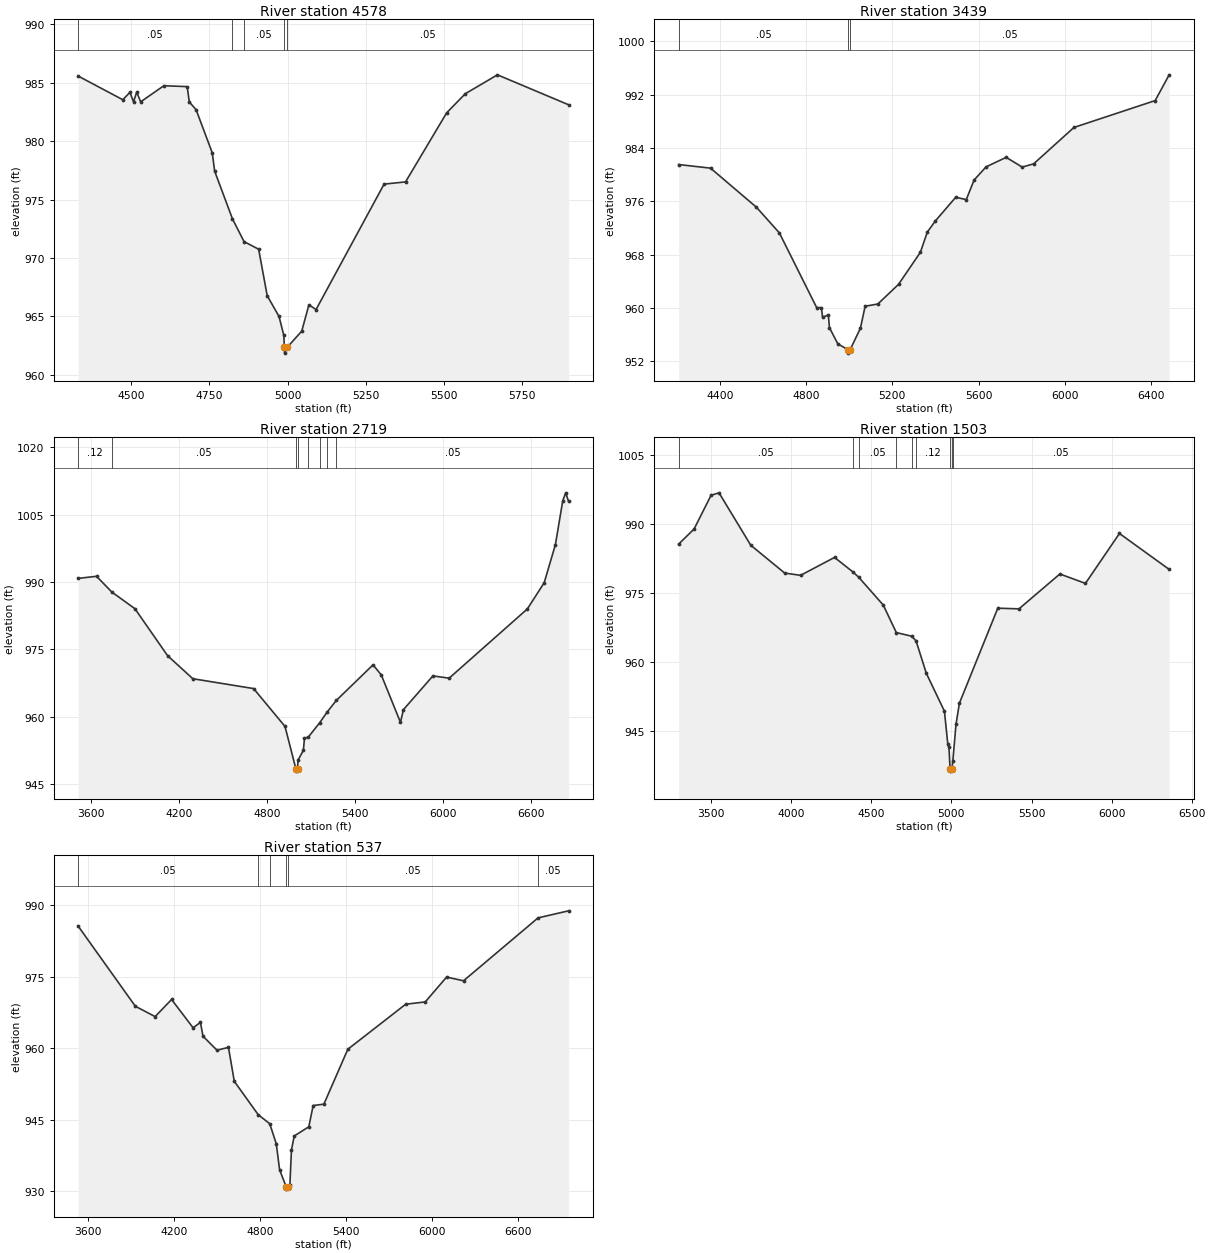
Type RM Length L Ch R = 1,4578,1139,1139,1139
BEGIN DESCRIPTION:
Mapping XS 03fb4c78
END DESCRIPTION:
XS GIS Cut Line= 2
      2842570.60     10251831.63      2841200.22     10251068.38
#Sta/Elev= 30
  4329.9  985.57  4472.9  983.54  4495.8  984.17  4507.2  983.36  4517.5  984.19
  4530.1  983.36  4604.4  984.74  4678.9  984.66  4685.6  983.35  4707.3  982.69
  4759.1  978.99  4766.7  977.43  4823.6  973.35  4860.7  971.40  4907.4  970.75
  4934.8  966.77  4972.5  965.00  4988.0  963.37  4989.6  962.36  4990.1  961.86
  4998.8  962.36  5045.2  963.74  5068.1  965.99  5091.0  965.59  5308.6  976.32
  5377.2  976.51  5508.7  982.42  5568.1  984.05  5671.0  985.67  5898.5  983.11
#Mann=5,-1,0
  4329.9    0.05       0  4823.6    0.12       0  4860.7    0.05       0
  4989.6    0.05       0  4998.8    0.05       0
Bank Sta=4989.6,4998.8
Exp/Cntr=0.3,0.1

Type RM Length L Ch R = 1,3439,720,720,720
BEGIN DESCRIPTION:
Mapping XS 31193fd7
END DESCRIPTION:
XS GIS Cut Line= 4
      2842865.73     10251171.90      2842449.07     10250685.79
      2841910.87     10250512.18      2840904.64     10250147.85
#Sta/Elev= 30
  4208.7  981.51  4356.7  980.97  4569.6  975.11  4676.0  971.26  4848.9  960.07
  4871.1  960.05  4876.4  958.62  4903.1  958.96  4908.4  957.05  4947.1  954.64
  4994.5  953.74  4995.0  953.24  5004.1  953.74  5052.1  956.98  5073.9  960.27
  5132.7  960.60  5228.9  963.55  5330.3  968.36  5362.3  971.38  5399.6  973.05
  5494.4  976.61  5543.1  976.25  5579.5  979.19  5635.0  981.16  5728.4  982.59
  5802.8  981.13  5856.0  981.62  6042.7  987.07  6419.7  991.10  6484.6  994.96
#Mann=3,-1,0
  4208.7    0.05       0  4994.5    0.05       0  5004.1    0.05       0
Bank Sta=4994.5,5004.1
Exp/Cntr=0.3,0.1

Type RM Length L Ch R = 1,2719,1216,1216,1216
BEGIN DESCRIPTION:
Mapping XS f9d9e4db
END DESCRIPTION:
XS GIS Cut Line= 4
      2843456.00     10251553.83      2842969.90     10250598.99
      2842726.85     10249887.18      2841216.42     10249730.93
#Sta/Elev= 30
  3511.2  990.81  3637.1  991.28  3740.8  987.79  3898.4  984.08  4120.8  973.64
  4293.1  968.50  4707.2  966.31  4921.2  957.89  4995.4  948.45  4995.9  947.95
  5006.5  948.45  5009.9  950.39  5046.5  952.58  5053.8  955.26  5080.3  955.53
  5158.1  958.74  5210.3  961.17  5271.3  963.69  5521.1  971.59  5577.3  969.34
  5708.0  958.79  5728.1  961.62  5929.1  969.13  6039.7  968.62  6572.5  984.02
  6687.2  989.84  6763.6  998.31  6813.8 1008.08  6833.9 1009.84  6853.3 1007.94
#Mann=8,-1,0
  3511.2    0.12       0  3740.8    0.05       0  4995.4    0.05       0
  5006.5    0.05       0  5080.3    0.12       0  5158.1    0.05       0
  5210.3    0.12       0  5271.3    0.05       0
Bank Sta=4995.4,5006.5
Exp/Cntr=0.3,0.1

Type RM Length L Ch R = 1,1503,966,966,966
BEGIN DESCRIPTION:
LITTLE SANDY CREEK 3.0
END DESCRIPTION:
XS GIS Cut Line= 3
      2844998.15     10250946.96      2843813.00     10249724.00
      2842644.55     10249029.04
#Sta/Elev= 30
  3297.0  985.67  3393.4  988.96  3499.4  996.28  3549.0  996.81  3747.1  985.43
  3959.1  979.38  4058.1  978.89  4270.3  982.78  4386.5  979.58  4421.8  978.45
  4574.4  972.43  4655.9  966.46  4752.1  965.66  4779.0  964.67  4843.2  957.62
  4956.4  949.37  4977.5  942.20  4984.7  941.53  4991.5  936.86  4992.0  936.36
  5002.8  936.86  5008.7  938.50  5028.5  946.51  5049.9  951.12  5289.5  971.75
  5421.9  971.61  5677.1  979.18  5836.8  977.14  6049.1  987.98  6359.5  980.18
#Mann=9,-1,0
  3297.0    0.05       0  4386.5    0.12       0  4421.8    0.05       0
  4655.9    0.12       0  4752.1    0.05       0  4779.0    0.12       0
  4991.5    0.07       0  5002.8    0.12       0  5008.7    0.05       0
Bank Sta=4991.5,5002.8
Exp/Cntr=0.3,0.1

Type RM Length L Ch R = 1,537,0,0,0
BEGIN DESCRIPTION:
LITTLE SANDY CREEK 1.0
END DESCRIPTION:
XS GIS Cut Line= 3
      2845103.94     10250476.86      2844495.50     10249141.00
      2842571.11     10248799.85
#Sta/Elev= 30
  3532.1  985.70  3931.8  968.84  4069.9  966.67  4184.5  970.26  4334.5  964.33
  4386.1  965.44  4403.6  962.56  4501.3  959.61  4581.5  960.21  4622.1  953.08
  4788.8  946.08  4869.5  944.17  4915.2  939.95  4938.2  934.50  4984.2  930.94
  4984.7  930.44  4995.5  930.94  5010.0  931.32  5020.9  938.66  5040.4  941.60
  5142.0  943.53  5172.5  948.00  5247.2  948.28  5414.3  959.81  5818.0  969.27
  5954.5  969.75  6103.4  974.97  6221.6  974.19  6741.6  987.40  6954.4  988.88
#Mann=6,-1,0
  3532.1    0.05       0  4788.8    0.12       0  4869.5    0.05       0
  4984.2    0.05       0  4995.5    0.05       0  6741.6    0.05       0
Bank Sta=4984.2,4995.5
Exp/Cntr=0.3,0.1

Chan Stop Cuts=-1