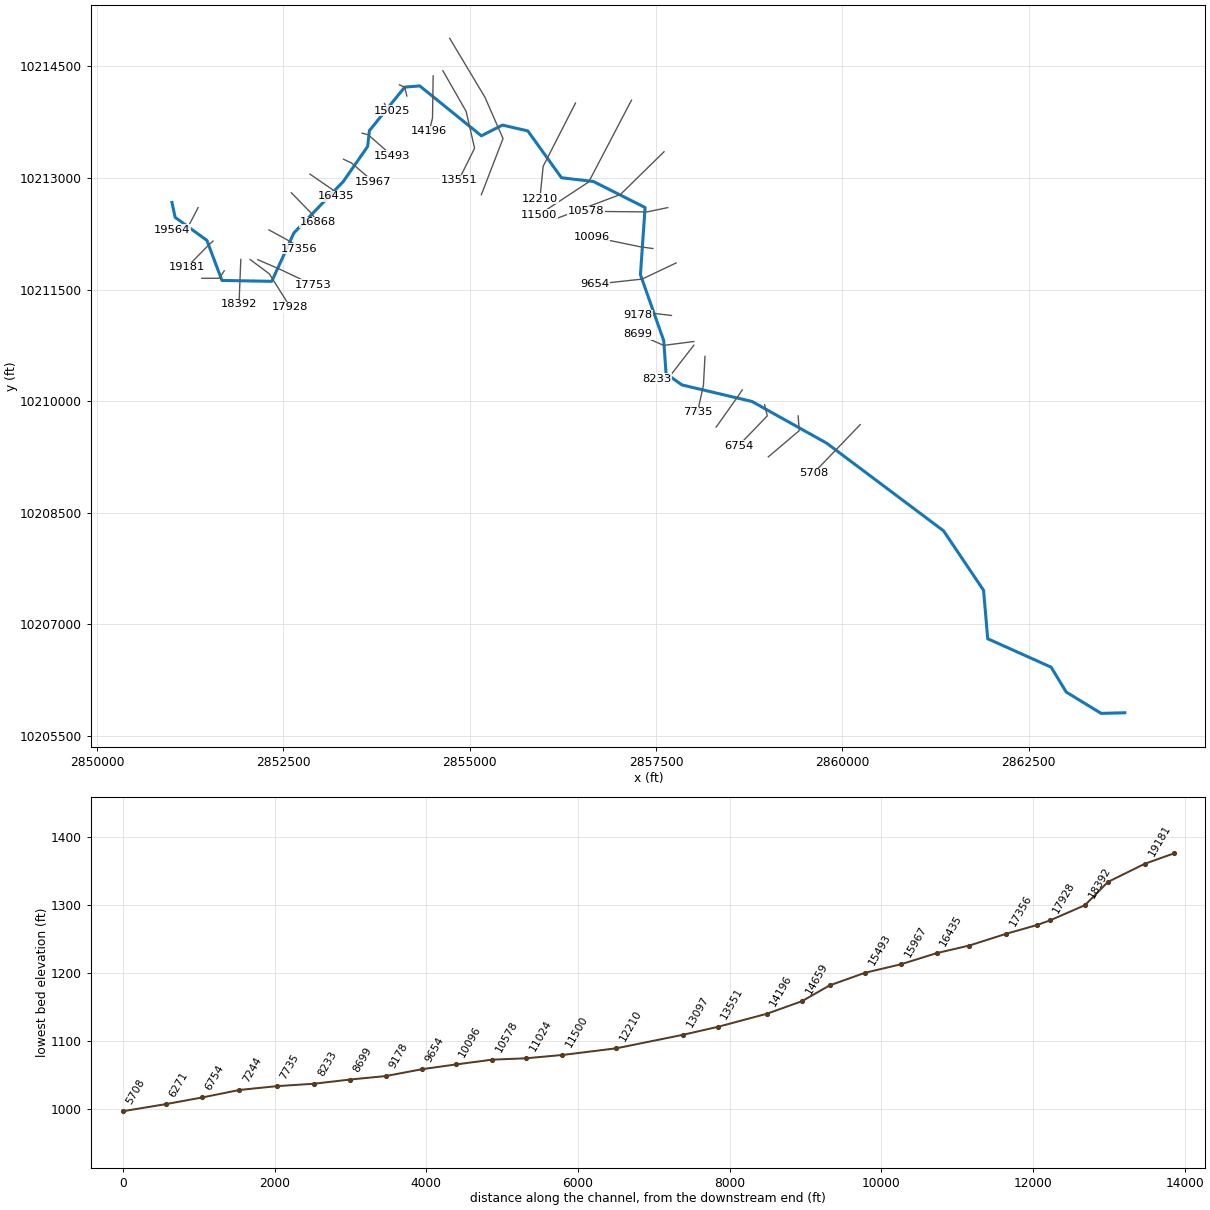
--- MOLASSES CREEK.prj (project) ---

Proj Title=MOLASSES CREEK Base Level Engineering
Current Plan=p01
Default Exp/Contr=0.3,0.1
English Units
Geom File=g01
Flow File=f01
Plan File=p01
Y Axis Title=Elevation
X Axis Title(PF)=Main Channel Distance
X Axis Title(XS)=Station
BEGIN DESCRIPTION:
MOLASSES CREEK
END DESCRIPTION:
DSS Export Rating Curves= 0
DSS Export Rating Curve Sorted= 0
DSS Export Volume Flow Curves= 0
DXF OffsetX= 0
DXF OffsetY= 0
DXF ScaleX= 1
DXF ScaleY= 10

--- MOLASSES CREEK.p01 (plan) ---

Plan Title=Multiple Run
Short Identifier=Multiple
Geom File=g01
Flow File=f01
Subcritical Flow
K Sum by GR= 0
Std Step Tol= 0.01
Critical Tol= 0.01
Num of Std Step Trials= 20
Max Error Tol= 0.3
Flow Tol Ratio= 0.001
Split Flow NTrial= 30
Split Flow Tol= 0.02
Split Flow Ratio= 0.02
Log Output Level= 0
Friction Slope Method= 1
Unsteady Friction Slope Method= 2
Unsteady Bridges Friction Slope Method= 1
Parabolic Critical Depth
Global Vel Dist=  1 , 1 , 1
Global Log Level= 0
CheckData=True
Encroach Param= -1, 0, 0, 0
BEGIN DESCRIPTION:
Multiple Run
END DESCRIPTION:

--- MOLASSES CREEK.f01 (steady flow) ---

Flow Title=Multiple
Number of Profiles=7
Profile Names=10-year,25-year,50-year,1pct_min,100-year,1pct_plu,500-year
River Rch & RM= MOLASSES CREEK,Reach-1,19564
     487     798    1840    1445    2643    4832    3926
River Rch & RM= MOLASSES CREEK,Reach-1,8233
     672    1122    2666    2072    3869    7223    5725
River Rch & RM= MOLASSES CREEK,Reach-1,5708
     896    1522    3699    2855    5417   10281    7980
River Rch & RM= MOLASSES CREEK,Reach-1,2874
    1004    1722    4069    3063    5968   11628    8776
Boundary for River Rch & Prof#=MOLASSES CREEK,Reach-1,1
Up Type=0
Dn Type=3
Dn Slope=0.005
Boundary for River Rch & Prof#=MOLASSES CREEK,Reach-1,2
Up Type=0
Dn Type=3
Dn Slope=0.005
Boundary for River Rch & Prof#=MOLASSES CREEK,Reach-1,3
Up Type=0
Dn Type=3
Dn Slope=0.005
Boundary for River Rch & Prof#=MOLASSES CREEK,Reach-1,4
Up Type=0
Dn Type=3
Dn Slope=0.005
Boundary for River Rch & Prof#=MOLASSES CREEK,Reach-1,5
Up Type=0
Dn Type=3
Dn Slope=0.005
Boundary for River Rch & Prof#=MOLASSES CREEK,Reach-1,6
Up Type=0
Dn Type=3
Dn Slope=0.005
Boundary for River Rch & Prof#=MOLASSES CREEK,Reach-1,7
Up Type=0
Dn Type=3
Dn Slope=0.005

--- MOLASSES CREEK.g01 (geometry) ---

Geom Title=Existing Conditions
Program Version=4.10

River Reach=MOLASSES CREEK  ,Reach-1
Reach XY= 30
        2851004.       10212673.      2851047.25       10212472.
       2851472.5       10212163.        2851675.       10211624.
       2852343.5       10211612.      2852639.25       10212261.
      2853302.25       10212953.      2853629.25       10213424.
      2853653.75       10213638.      2854126.75       10214222.
       2854328.5       10214239.       2855155.5       10213568.
      2855437.75       10213712.       2855778.5       10213634.
      2856230.25       10213004.       2856658.5       10212954.
      2857352.25       10212604.      2857289.75       10211701.
      2857602.25       10210814.       2857633.5       10210370.
      2857848.25       10210219.        2858787.       10209997.
      2859789.75       10209436.      2861355.75       10208259.
      2861893.25       10207459.        2861949.       10206808.
       2862799.5       10206426.        2863002.       10206092.
      2863470.25       10205805.      2863787.75       10205813.

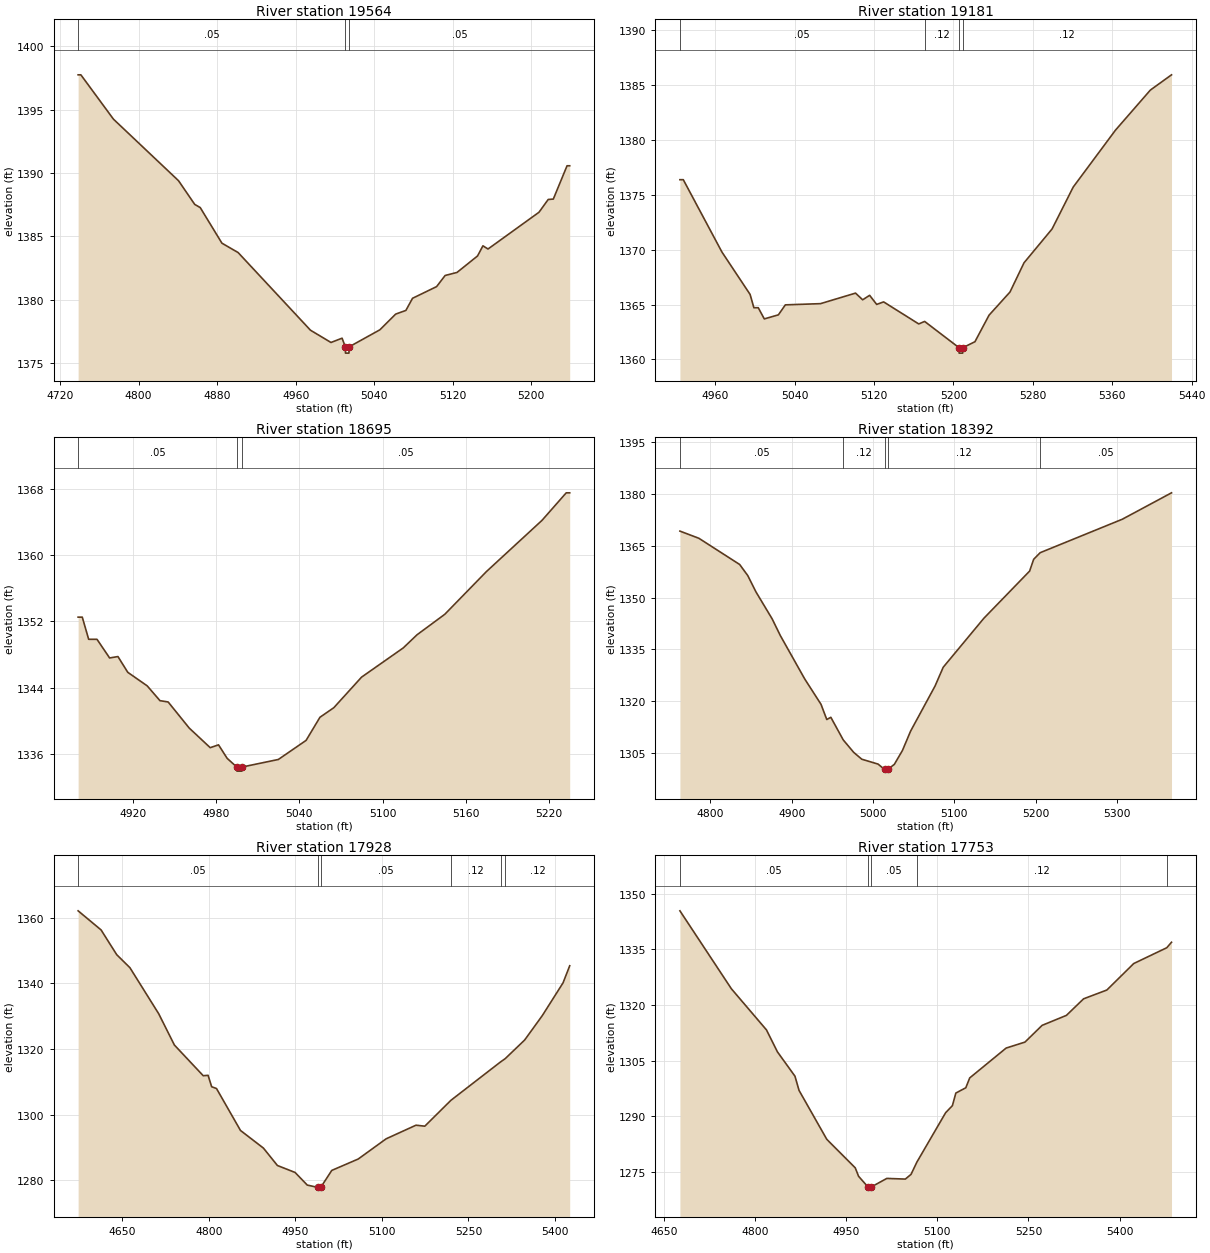
Type RM Length L Ch R = 1 ,19564   ,383,383,383
BEGIN DESCRIPTION:
MOLASSES CREEK 42.0
END DESCRIPTION:
XS GIS Cut Line= 3
      2851355.68      10212603.1        2851235.       10212371.
      2851005.64      10212303.1
#Sta/Elev= 30
  4738.4 1397.74  4741.2 1397.74  4774.4 1394.24  4840.7 1389.38  4857.2 1387.51
  4862.8 1387.26  4884.9 1384.45  4901.4 1383.71  4975.1 1377.58    4996 1376.61
  5007.3 1376.95  5010.6 1376.27  5010.8 1375.77  5014.3 1375.77  5014.6 1376.27
  5045.8 1377.61  5061.9 1378.85  5072.3 1379.14  5079.1  1380.1  5103.6 1381.02
  5112.3  1381.9  5124.4 1382.14  5145.3 1383.44  5150.8 1384.24    5156 1383.99
  5207.9 1386.89  5217.3  1387.9  5222.5 1387.93  5236.5 1390.56  5239.2 1390.56
#Mann= 3 ,-1 , 0
  4738.4     .05       0  5010.6     .05       0  5014.6     .05       0
Bank Sta=5010.6,5014.6
XS Rating Curve= 0 ,0
Exp/Cntr=0.3,0.1

Type RM Length L Ch R = 1 ,19181   ,486,486,486
BEGIN DESCRIPTION:
MOLASSES CREEK 41.0
END DESCRIPTION:
XS GIS Cut Line= 3
      2851555.71     10212153.13      2851499.25       10212103.
      2851205.66     10211803.08
#Sta/Elev= 30
  4924.5 1376.38  4927.9 1376.38  4966.8 1369.79  4995.2 1365.92    4999 1364.71
  5003.4 1364.71  5009.5 1363.69  5023.7 1364.06  5030.7 1364.97  5066.1 1365.08
  5101.4 1366.04  5108.6 1365.43  5115.6 1365.84  5122.7 1365.01  5129.7 1365.24
  5165.1 1363.23    5171 1363.46  5205.6 1361.07  5205.8 1360.57  5209.3 1360.57
  5209.6 1361.07  5221.7 1361.61  5235.9 1364.03    5257 1366.14  5271.1  1368.8
  5299.4 1371.89  5320.7 1375.71  5363.2 1380.89  5398.4 1384.55  5419.7 1385.94
#Mann= 4 ,-1 , 0
  4924.5     .05       0    5171     .12       0  5205.6     .05       0
  5209.6     .12       0
Bank Sta=5205.6,5209.6
XS Rating Curve= 0 ,0
Exp/Cntr=0.3,0.1

Type RM Length L Ch R = 1 ,18695   ,303,303,303
BEGIN DESCRIPTION:
MOLASSES CREEK 40.0
END DESCRIPTION:
XS GIS Cut Line= 3
       2851705.7     10211753.14       2851640.5       10211653.
       2851405.7     10211653.11
#Sta/Elev= 30
  4880.5 1352.52  4883.5 1352.52  4888.1 1349.84  4894.1 1349.84  4903.2 1347.58
  4909.2 1347.75  4916.3 1345.84  4930.3  1344.2  4939.5 1342.41  4945.4 1342.25
  4960.6 1339.09  4975.7 1336.72  4981.7 1337.06  4987.9 1335.43  4994.8 1334.38
    4995 1333.88  4998.5 1333.88  4998.8 1334.38  5024.8 1335.29  5044.8  1337.6
  5054.8  1340.4  5064.8 1341.56  5084.8 1345.26  5114.8 1348.79  5124.8 1350.39
  5144.8 1352.87  5174.8 1358.04  5214.8 1364.23  5232.3 1367.57  5234.8 1367.57
#Mann= 3 ,-1 , 0
  4880.5     .05       0  4994.8     .05       0  4998.8     .05       0
Bank Sta=4994.8,4998.8
XS Rating Curve= 0 ,0
Exp/Cntr=0.3,0.1

Type RM Length L Ch R = 1 ,18392   ,464,464,464
BEGIN DESCRIPTION:
Mapping XS 38f000a5
END DESCRIPTION:
XS GIS Cut Line= 2
      2851928.04     10211906.41       2851903.7      10211302.7
#Sta/Elev= 30
  4762.7 1369.24    4786 1367.16  4836.1 1359.58  4846.1 1356.36  4856.1 1351.66
  4876.1 1343.81  4886.1    1339  4916.1 1326.43  4936.1  1319.1  4943.2 1314.69
  4948.2 1315.33  4963.4  1308.8  4976.2  1305.2  4986.2  1303.2  5006.2 1301.79
  5014.2 1300.25  5014.5 1299.75    5018 1299.75  5018.2 1300.25  5026.2  1301.7
  5036.2 1305.73  5046.2 1311.32  5076.3  1324.4  5086.3 1329.82  5136.3 1344.01
  5192.5 1357.66  5197.5 1361.08  5205.5 1362.99  5306.4 1372.67  5366.9 1380.32
#Mann= 5 ,-1 , 0
  4762.7     .05       0  4963.4     .12       0  5014.2     .07       0
  5018.2     .12       0  5205.5     .05       0
Bank Sta=5014.2,5018.2
XS Rating Curve= 0 ,0
Exp/Cntr=0.3,0.1

Type RM Length L Ch R = 1 ,17928   ,175,175,175
BEGIN DESCRIPTION:
MOLASSES CREEK 39.0
END DESCRIPTION:
XS GIS Cut Line= 3
      2852053.19      10211905.2       2852310.4     10211712.88
      2852593.09     10211263.34
#Sta/Elev= 30
  4573.4 1362.17  4613.2 1356.34  4640.3 1348.79  4663.2 1344.81  4713.2 1330.73
  4740.3 1321.21  4790.3 1311.84  4798.7 1311.97  4804.9 1308.48  4813.3 1307.93
  4854.9 1295.13  4894.6 1289.76  4918.9 1284.44  4949.5 1282.32  4970.7 1278.46
  4989.9 1277.73  4990.1 1277.23  4993.9 1277.73  5013.1 1282.94    5059 1286.42
  5107.3 1292.58  5159.1 1296.74  5174.4 1296.44  5219.7 1304.34  5305.7 1316.05
  5313.7 1317.04  5347.5 1322.74  5378.1 1330.19  5414.1  1340.2  5425.6  1345.4
#Mann= 6 ,-1 , 0
  4573.4     .05       0  4989.9     .05       0  4993.9     .05       0
  5219.7     .12       0  5305.7     .05       0  5313.7     .12       0
Bank Sta=4989.9,4993.9
XS Rating Curve= 0 ,0
Exp/Cntr=0.3,0.1

Type RM Length L Ch R = 1 ,17753   ,397,397,397
BEGIN DESCRIPTION:
MOLASSES CREEK 38.0
END DESCRIPTION:
XS GIS Cut Line= 3
      2852155.72      10211903.1        2852453.       10211774.
      2852891.95     10211566.32
#Sta/Elev= 30
  4675.9 1345.42  4760.7 1324.38  4818.5 1313.28  4836.5 1307.37  4865.4  1300.8
  4872.1 1296.97  4917.8 1283.77  4964.7 1276.07  4970.2 1273.79  4986.1 1270.83
  4986.4 1270.33  4990.1 1270.83  5016.7 1273.22  5047.2 1273.04  5056.6 1274.32
  5066.2 1277.62  5113.6 1290.96  5124.7 1292.85  5130.4 1296.25  5146.8 1297.68
  5153.2 1300.33  5213.2 1308.39  5244.2    1310  5272.5 1314.52  5312.5 1317.21
  5340.8 1321.68  5379.1 1324.05  5423.4  1331.2  5477.8 1335.46  5485.6 1336.94
#Mann= 5 ,-1 , 0
  4675.9     .05       0  4986.1     .05       0  4990.1     .05       0
  5066.2     .12       0  5477.8     .05       0
Bank Sta=4986.1,4990.1
XS Rating Curve= 0 ,0
Exp/Cntr=0.3,0.1

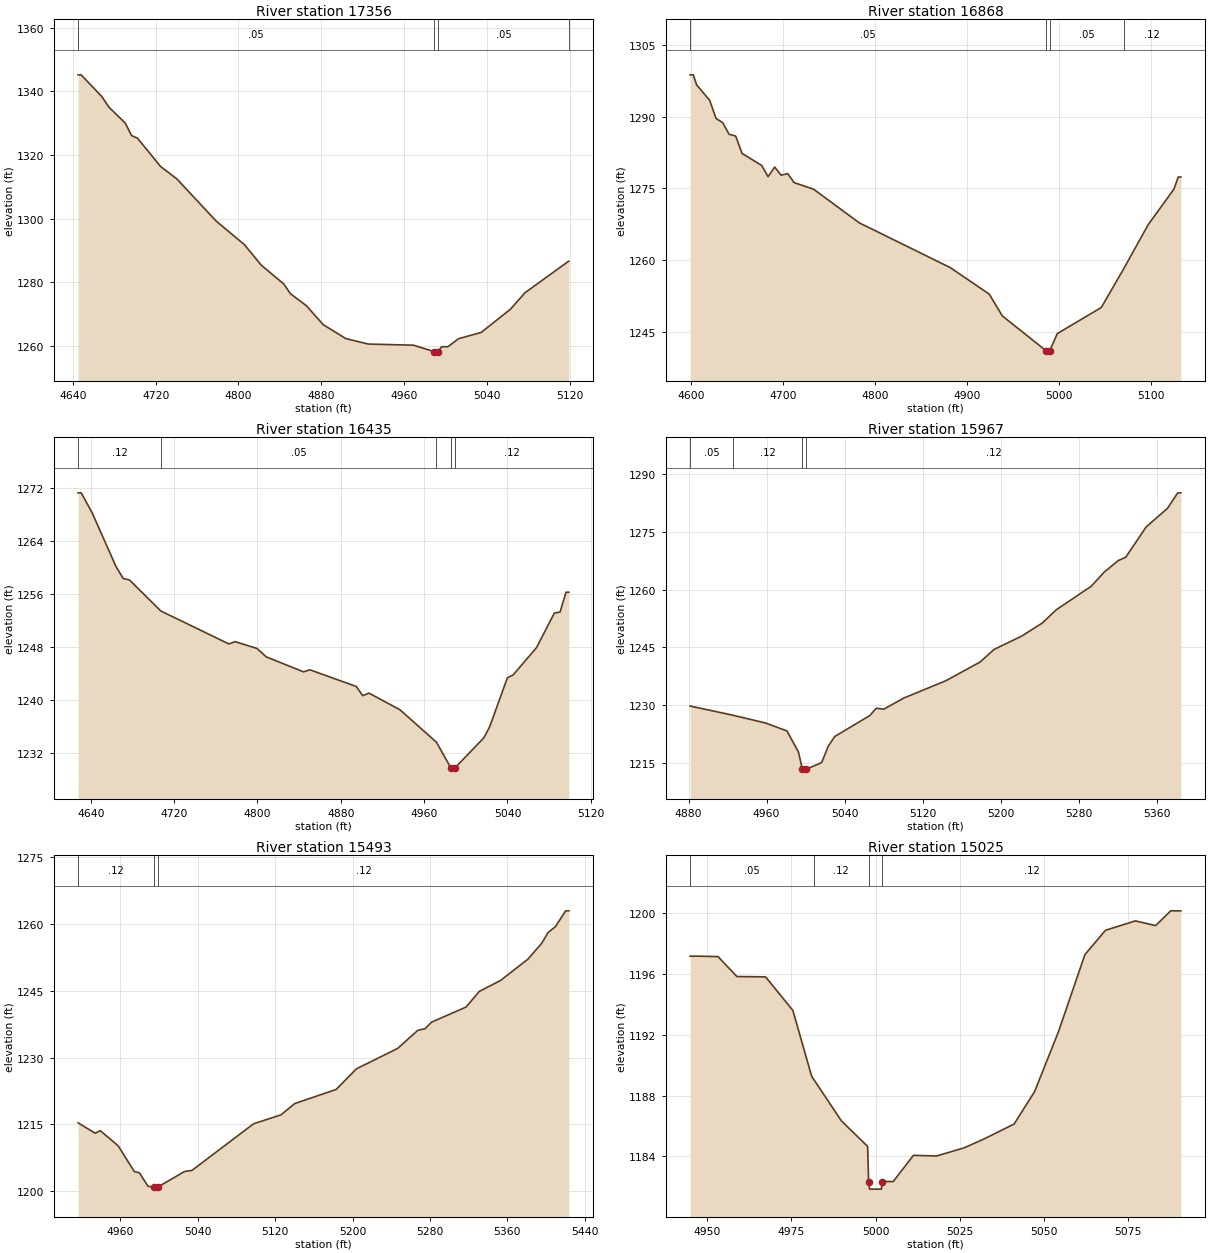
Type RM Length L Ch R = 1 ,17356   ,488,488,488
BEGIN DESCRIPTION:
MOLASSES CREEK 37.0
END DESCRIPTION:
XS GIS Cut Line= 3
      2852305.67     10212303.12      2852617.25       10212133.
       2852705.7      10212053.1
#Sta/Elev= 30
    4645 1345.19  4647.9 1345.19  4667.8 1338.42  4674.9    1335  4690.6 1330.03
  4696.7 1326.12  4702.4 1325.28  4724.8 1316.38  4740.4 1312.51  4778.4 1299.27
  4805.9  1291.8    4822 1285.41  4843.8  1279.5  4850.1 1276.46  4865.7 1272.65
  4881.8 1266.74  4903.6 1262.36  4925.4 1260.63  4969.1 1260.27  4988.9 1258.28
  4989.2 1257.78  4992.9 1258.28  4996.3 1259.79  5002.3 1259.79  5012.7 1262.33
  5034.4 1264.26  5062.7 1271.55  5076.9 1276.76  5118.9 1286.63  5119.2 1286.63
#Mann= 4 ,-1 , 0
    4645     .05       0  4988.9     .05       0  4992.9     .05       0
  5118.9     .12       0
Bank Sta=4988.9,4992.9
XS Rating Curve= 0 ,0
Exp/Cntr=0.3,0.1

Type RM Length L Ch R = 1 ,16868   ,433,433,433
BEGIN DESCRIPTION:
MOLASSES CREEK 36.0
END DESCRIPTION:
XS GIS Cut Line= 3
      2852605.65     10212803.14      2852885.25       10212515.
      2852955.68     10212403.12
#Sta/Elev= 30
  4598.5 1298.81    4602 1298.81  4605.6 1296.71  4619.8 1293.46  4626.7 1289.67
  4633.9  1288.8  4640.9 1286.35  4648.1 1285.97    4655 1282.33  4676.4  1279.8
  4683.3 1277.46  4690.5 1279.48  4697.5 1277.77  4704.6  1278.1  4711.6 1276.22
  4732.9 1274.82  4782.3  1267.8  4881.4  1258.4  4923.8 1252.84    4938 1248.28
  4985.6 1240.97  4985.8 1240.47  4989.6 1240.97  4997.8 1244.56  5045.7 1250.04
  5070.1 1258.18  5096.8 1267.44  5124.6 1274.83  5129.3 1277.39  5132.2 1277.39
#Mann= 4 ,-1 , 0
  4598.5     .05       0  4985.6     .05       0  4989.6     .05       0
  5070.1     .12       0
Bank Sta=4985.6,4989.6
XS Rating Curve= 0 ,0
Exp/Cntr=0.3,0.1

Type RM Length L Ch R = 1 ,16435   ,468,468,468
BEGIN DESCRIPTION:
MOLASSES CREEK 35.0
END DESCRIPTION:
XS GIS Cut Line= 3
       2852855.7      10213053.1      2853162.25       10212842.
      2853205.67     10212753.14
#Sta/Elev= 30
  4627.8  1271.2  4630.8  1271.2  4641.3 1268.19  4664.2 1260.09  4671.1 1258.29
  4677.1 1258.07  4707.2 1253.39  4772.5 1248.42  4778.6 1248.76  4799.6 1247.73
  4808.4 1246.47  4844.2 1244.21  4850.3 1244.52  4894.9    1242    4901 1240.62
  4907.1    1241  4936.9 1238.48  4971.8  1233.6  4985.6 1229.74  4985.8 1229.24
  4989.6 1229.74  5017.3 1234.26  5022.9 1235.92  5039.9 1243.32  5045.4 1243.74
  5067.9 1247.87  5084.9 1253.05  5090.5 1253.24  5096.2 1256.21  5098.9 1256.21
#Mann= 5 ,-1 , 0
  4627.8     .12       0  4707.2     .05       0  4971.8     .12       0
  4985.6     .07       0  4989.6     .12       0
Bank Sta=4985.6,4989.6
XS Rating Curve= 0 ,0
Exp/Cntr=0.3,0.1

Type RM Length L Ch R = 1 ,15967   ,474,474,474
BEGIN DESCRIPTION:
MOLASSES CREEK 34.0
END DESCRIPTION:
XS GIS Cut Line= 3
      2853305.72      10213253.1        2853413.       10213203.
      2853705.65     10212953.14
#Sta/Elev= 30
  4881.6 1229.81  4925.1 1227.46  4958.8 1225.43  4980.9 1223.36  4992.7 1217.89
  4996.7 1213.44    4997 1212.94  5000.5 1212.94  5000.7 1213.44  5016.5 1215.15
  5023.1 1219.33  5029.8  1221.9  5065.9 1227.36  5072.5 1229.25  5080.2 1229.01
    5101 1231.92  5143.9 1236.38    5179 1241.24  5193.3  1244.5  5221.8 1247.98
  5242.7 1251.34  5256.9 1254.75  5292.8 1260.86  5306.3 1264.57  5320.6 1267.53
  5328.3 1268.41  5349.2 1276.26  5371.1 1281.09  5381.6  1285.1  5384.8  1285.1
#Mann= 4 ,-1 , 0
  4881.6     .05       0  4925.1     .12       0  4996.7     .07       0
  5000.7     .12       0
Bank Sta=4996.7,5000.7
XS Rating Curve= 0 ,0
Exp/Cntr=0.3,0.1

Type RM Length L Ch R = 1 ,15493   ,468,468,468
BEGIN DESCRIPTION:
MOLASSES CREEK 33.0
END DESCRIPTION:
XS GIS Cut Line= 3
      2853555.65     10213603.12      2853636.75       10213582.
      2853955.71     10213303.09
#Sta/Elev= 30
  4916.2 1215.34  4933.9    1213  4939.1 1213.59  4957.6 1210.19  4974.4 1204.39
  4979.6 1204.11  4988.6 1201.07  4994.9 1200.95  4995.1 1200.45  4998.9 1200.95
  5026.4 1204.42    5034 1204.66  5097.6 1215.11  5126.1 1217.14  5140.3 1219.67
  5183.1 1222.83  5203.9 1227.44  5246.7 1232.05  5267.5 1236.11  5275.1 1236.47
  5281.8 1237.95  5317.4 1241.33  5331.1 1244.85    5353  1247.3  5381.4 1252.09
  5395.7 1255.68  5402.3 1258.08  5409.9  1259.4  5420.4 1262.94  5423.7 1262.94
#Mann= 3 ,-1 , 0
  4916.2     .12       0  4994.9     .07       0  4998.9     .12       0
Bank Sta=4994.9,4998.9
XS Rating Curve= 0 ,0
Exp/Cntr=0.3,0.1

Type RM Length L Ch R = 1 ,15025   ,366,366,366
BEGIN DESCRIPTION:
MOLASSES CREEK 32.0
END DESCRIPTION:
XS GIS Cut Line= 3
       2853855.7     10214003.08      2853880.75       10213954.
       2853955.7      10213903.1
#Sta/Elev= 28
  4944.9 1197.16  4947.7 1197.16  4953.2 1197.13  4958.8 1195.82  4967.3  1195.8
  4975.4  1193.6    4981 1189.26  4981.7 1189.03  4989.8 1186.34  4997.6 1184.66
  4997.9 1182.35  4998.2 1181.85  5001.7 1181.85  5001.9 1182.35  5005.2 1182.35
  5011.2 1184.07  5018.1 1184.03  5026.2 1184.56  5032.2 1185.15  5041.1 1186.13
  5047.2 1188.27  5054.3 1192.22  5062.1 1197.26  5068.2 1198.86  5077.1 1199.48
  5083.1 1199.17  5087.6 1200.14  5090.6 1200.14
#Mann= 4 ,-1 , 0
  4944.9     .05       0  4981.7     .12       0  4997.9     .07       0
  5001.9     .12       0
Bank Sta=4997.9,5001.9
XS Rating Curve= 0 ,0
Exp/Cntr=0.3,0.1

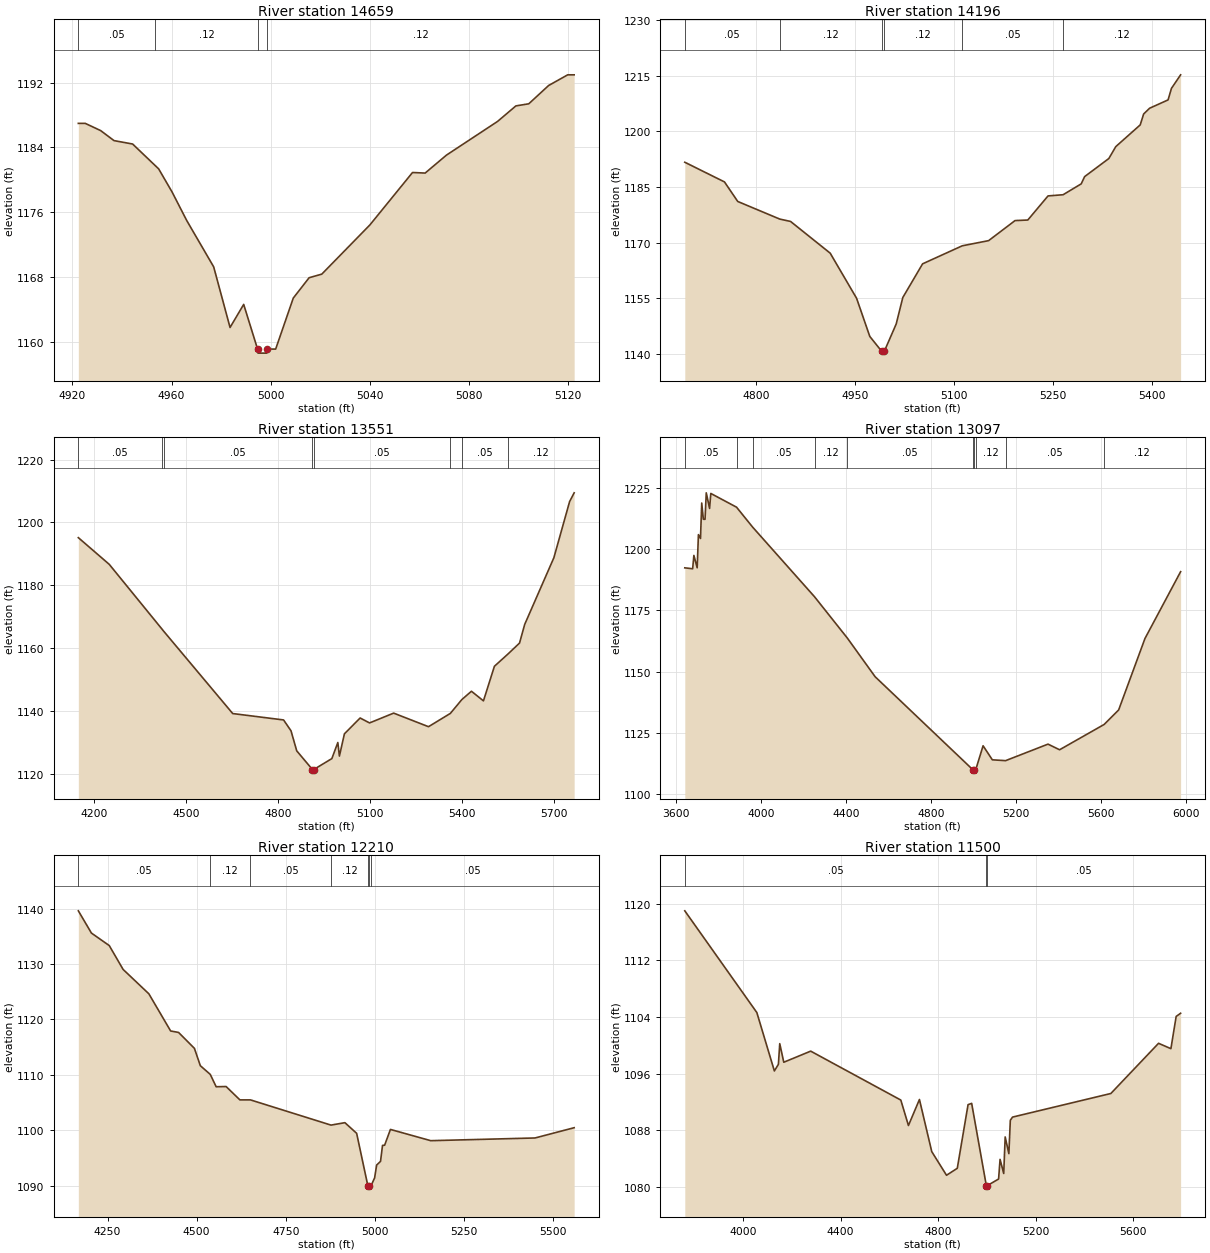
Type RM Length L Ch R = 1 ,14659   ,463,463,463
BEGIN DESCRIPTION:
MOLASSES CREEK 31.0
END DESCRIPTION:
XS GIS Cut Line= 3
      2854055.66     10214253.12      2854126.75       10214222.
      2854155.69     10214103.07
#Sta/Elev= 30
  4922.4 1186.98  4925.2 1186.98  4931.4 1186.09  4936.8 1184.85  4944.3 1184.43
  4953.5 1181.74  4954.8 1181.36  4960.2 1178.51  4966.1 1174.99    4977 1169.25
  4983.6 1161.76  4989.1 1164.61  4994.7 1159.09  4994.9 1158.59  4998.4 1158.59
  4998.7 1159.09    5002 1159.09  5009.1 1165.39  5015.5 1167.91  5020.6 1168.35
    5040 1174.43  5057.2 1180.91  5062.3 1180.84  5070.9 1183.06  5091.5 1187.22
  5098.9 1189.14  5104.1  1189.4  5112.1 1191.66  5119.8 1192.98  5122.4 1192.98
#Mann= 4 ,-1 , 0
  4922.4     .05       0  4953.5     .12       0  4994.7     .07       0
  4998.7     .12       0
Bank Sta=4994.7,4998.7
XS Rating Curve= 0 ,0
Exp/Cntr=0.3,0.1

Type RM Length L Ch R = 1 ,14196   ,645,645,645
BEGIN DESCRIPTION:
Mapping XS e7e4ecfe
END DESCRIPTION:
XS GIS Cut Line= 3
      2854508.74     10214373.25      2854500.06     10213809.05
      2854456.81      10213627.4
#Sta/Elev= 30
  4692.5 1191.68  4752.6 1186.37  4772.7 1181.09  4836.3 1176.34  4852.7  1175.7
  4912.7 1167.14  4952.7 1154.96  4972.7 1144.66  4990.7 1140.65  4990.9 1140.15
  4994.7 1140.65  5012.7 1148.01  5022.7 1155.16  5052.7 1164.26  5112.7 1169.12
  5152.7 1170.52  5192.7 1175.93    5212 1176.08  5242.7 1182.59  5265.5 1182.91
  5292.9 1185.84  5298.1  1187.8  5334.8 1192.69  5345.3  1195.9  5382.3 1201.76
  5387.5 1204.71  5396.5 1206.26  5424.5 1208.51  5429.6 1211.62  5443.5 1215.28
#Mann= 6 ,-1 , 0
  4692.5     .05       0  4836.3     .12       0  4990.7     .07       0
  4994.7     .12       0  5112.7     .05       0  5265.5     .12       0
Bank Sta=4990.7,4994.7
XS Rating Curve= 0 ,0
Exp/Cntr=0.3,0.1

Type RM Length L Ch R = 1 ,13551   ,454,454,454
BEGIN DESCRIPTION:
Mapping XS 92fb8158
END DESCRIPTION:
XS GIS Cut Line= 4
      2854638.93     10214442.77      2854951.45     10213895.86
       2855064.3     10213401.07      2854850.78     10212969.83
#Sta/Elev= 30
  4147.9 1195.17  4248.8 1186.69  4421.3 1166.07  4426.3 1165.46  4651.9 1139.26
  4817.9 1137.23  4842.2 1133.77  4860.9  1127.4  4912.2 1121.46  4912.4 1120.96
  4916.2 1121.46  4975.5 1124.94    4995 1130.05  5000.2 1125.75  5016.5 1132.81
  5067.8 1137.85  5098.6 1136.28  5177.3  1139.4    5291 1135.08  5362.4 1139.31
    5400 1143.72  5431.2 1146.35  5470.4 1143.29  5506.2 1154.29  5550.5 1158.19
  5588.2 1161.67    5605 1167.58  5700.3 1188.79  5751.7 1206.65  5766.5 1209.42
#Mann= 8 ,-1 , 0
  4147.9     .05       0  4421.3     .12       0  4426.3     .05       0
  4912.2     .03       0  4916.2     .05       0  5362.4     .12       0
    5400     .05       0  5550.5     .12       0
Bank Sta=4912.2,4916.2
XS Rating Curve= 0 ,0
Exp/Cntr=0.3,0.1

Type RM Length L Ch R = 1 ,13097   ,887,887,887
BEGIN DESCRIPTION:
Mapping XS 1615558e
END DESCRIPTION:
XS GIS Cut Line= 4
      2854730.67     10214878.14      2855203.19     10214086.83
      2855446.24     10213531.28      2855155.31     10212776.34
#Sta/Elev= 30
  3639.7 1192.41  3676.7 1192.03  3682.5 1197.48  3698.1 1192.42  3703.9 1205.97
  3713.7  1204.4  3719.5 1218.87  3727.1 1212.24  3735.1 1212.22  3740.9 1223.03
  3756.5 1216.66  3762.3 1222.78  3883.6 1217.17  3959.5 1209.03  4251.2 1180.61
  4405.9 1163.74  4536.8 1147.97  4998.4 1109.93  4998.6 1109.43  5002.4 1109.93
  5012.1 1110.31  5045.7 1119.78  5089.3 1114.05  5151.7  1113.7  5351.7 1120.45
  5406.3 1118.15  5616.1 1128.47  5684.7  1134.4  5808.8 1163.58  5976.8 1190.84
#Mann= 10 ,-1 , 0
  3639.7     .05       0  3883.6     .12       0  3959.5     .05       0
  4251.2     .12       0  4405.9     .05       0  4998.4     .05       0
  5002.4     .05       0  5012.1     .12       0  5151.7     .05       0
  5616.1     .12       0
Bank Sta=4998.4,5002.4
XS Rating Curve= 0 ,0
Exp/Cntr=0.3,0.1

Type RM Length L Ch R = 1 ,12210   ,710,710,710
BEGIN DESCRIPTION:
Mapping XS 67782570
END DESCRIPTION:
XS GIS Cut Line= 3
      2856418.44     10214008.67      2855984.44     10213158.01
      2855941.03     10212723.95
#Sta/Elev= 30
    4168  1139.6  4204.7 1135.59  4254.8 1133.33  4293.6 1129.03  4365.9 1124.63
    4427 1117.92  4449.2 1117.66  4493.7 1114.79  4510.3 1111.66  4538.2 1110.09
  4554.7 1107.86  4582.6  1107.9  4621.4 1105.49    4651 1105.49    4877 1100.94
    4916 1101.38  4948.9 1099.46  4980.7 1089.89  4980.9 1089.39  4984.7 1089.89
  4989.3 1090.01  4999.3 1091.41    5005 1093.73  5015.9  1094.4  5021.5 1097.28
  5027.4 1097.31  5043.7 1100.16  5156.9 1098.13  5449.5 1098.62  5559.2 1100.47
#Mann= 7 ,-1 , 0
    4168     .05       0  4538.2     .12       0    4651     .05       0
    4877     .12       0  4980.7     .03       0  4984.7     .12       0
  4989.3     .05       0
Bank Sta=4980.7,4984.7
XS Rating Curve= 0 ,0
Exp/Cntr=0.3,0.1

Type RM Length L Ch R = 1 ,11500   ,476,476,476
BEGIN DESCRIPTION:
MOLASSES CREEK 24.0
END DESCRIPTION:
XS GIS Cut Line= 3
      2857169.37     10214046.57        2856596.       10212948.
      2855932.36     10212510.09
#Sta/Elev= 30
  3760.8 1119.02  4056.4 1104.63  4128.3 1096.37  4144.8  1097.3  4150.4 1100.23
  4166.9  1097.6  4277.3 1099.17  4647.1 1092.25  4678.4 1088.65  4723.5 1092.33
    4774 1084.96  4834.6 1081.61  4878.8  1082.6    4923  1091.6  4937.8 1091.78
  4997.9 1080.15  4998.2 1079.65  5001.9 1080.15  5048.3 1081.08  5054.3 1083.86
  5069.3 1081.86  5075.3 1087.03  5090.4 1084.67  5096.4 1089.39  5105.5 1089.84
  5508.9 1093.18  5704.6 1100.28  5755.2 1099.52  5776.8 1104.08  5795.1 1104.53
#Mann= 3 ,-1 , 0
  3760.8     .05       0  4997.9     .05       0  5001.9     .05       0
Bank Sta=4997.9,5001.9
XS Rating Curve= 0 ,0
Exp/Cntr=0.3,0.1

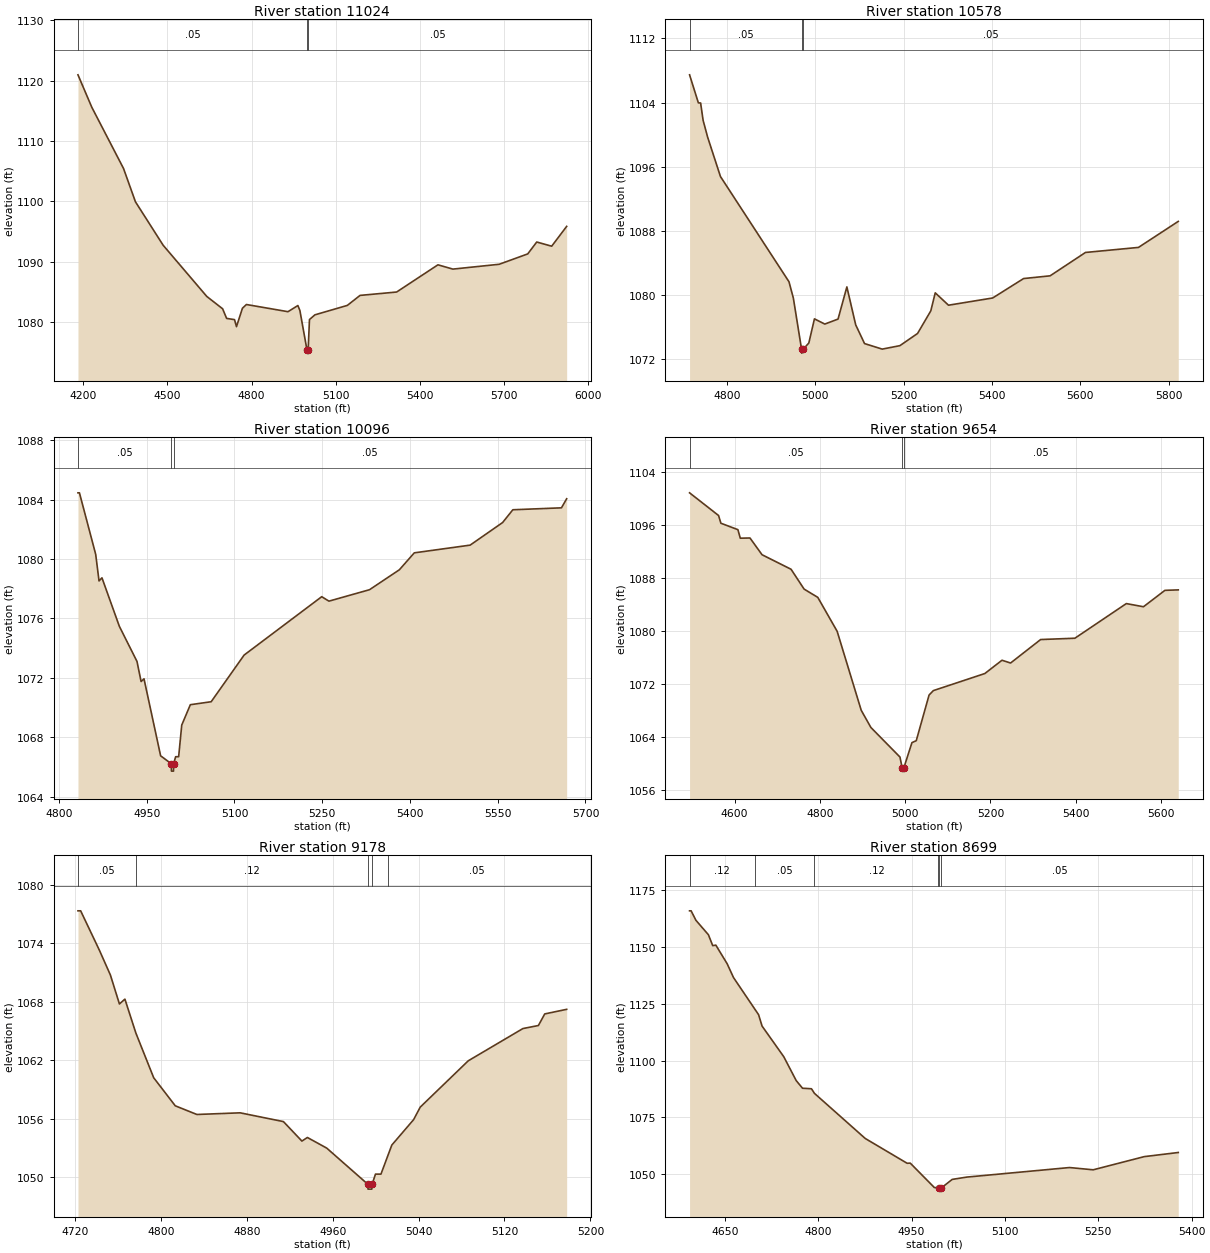
Type RM Length L Ch R = 1 ,11024   ,446,446,446
BEGIN DESCRIPTION:
MOLASSES CREEK 23.0
END DESCRIPTION:
XS GIS Cut Line= 3
      2857605.67     10213353.09        2857021.       10212779.
      2856155.73     10212453.13
#Sta/Elev= 30
  4180.6 1120.96  4230.1 1115.57  4343.2 1105.43  4385.7 1099.91  4484.7  1092.7
  4640.3 1084.22  4696.8 1082.17    4711 1080.58  4739.3 1080.37  4746.3 1079.21
  4767.5 1082.26  4781.7 1082.88  4930.1 1081.69  4965.4 1082.71  4972.6 1081.88
    4998 1075.32  4998.3 1074.82    5002 1075.32  5006.8 1080.39  5026.3 1081.17
  5141.8 1082.73  5187.3 1084.39  5317.8 1084.95  5465.2 1089.46  5518.6 1088.75
  5683.8 1089.55  5785.7 1091.27  5817.8 1093.24  5871.2 1092.55  5924.6 1095.83
#Mann= 3 ,-1 , 0
  4180.6     .05       0    4998     .03       0    5002     .05       0
Bank Sta=4998,5002
XS Rating Curve= 0 ,0
Exp/Cntr=0.3,0.1

Type RM Length L Ch R = 1 ,10578   ,482,482,482
BEGIN DESCRIPTION:
MOLASSES CREEK 22.0
END DESCRIPTION:
XS GIS Cut Line= 3
      2857655.65      10212603.1      2857377.25       10212545.
      2856555.69     10212553.11
#Sta/Elev= 30
  4715.6 1107.46  4735.5 1103.97  4740.6 1103.95  4746.2  1101.8  4756.4 1099.71
  4785.5 1094.79  4940.6 1081.68  4950.5 1079.64    4969 1073.29  4969.2 1072.79
    4973 1073.29  4985.5 1074.05  4998.2 1077.06  5021.6 1076.41  5051.6 1077.03
  5071.6 1081.04  5091.6 1076.31  5111.6 1073.98  5151.6 1073.29  5191.6 1073.72
  5231.6 1075.24  5261.6 1078.06  5271.6  1080.3  5301.6 1078.76  5401.6 1079.66
  5471.6 1082.08  5531.6 1082.42  5611.6 1085.33  5731.6 1085.96  5821.6  1089.2
#Mann= 3 ,-1 , 0
  4715.6     .05       0    4969     .05       0    4973     .05       0
Bank Sta=4969,4973
XS Rating Curve= 0 ,0
Exp/Cntr=0.3,0.1

Type RM Length L Ch R = 1 ,10096   ,442,442,442
BEGIN DESCRIPTION:
MOLASSES CREEK 21.0
END DESCRIPTION:
XS GIS Cut Line= 3
      2857455.68     10212053.11      2857289.75       10212076.
      2856635.56     10212210.63
#Sta/Elev= 30
  4832.5 1084.45    4835 1084.45  4862.8 1080.31  4868.5 1078.52  4873.5 1078.73
  4903.2 1075.47  4933.4  1073.1  4940.4 1071.75  4945.4 1071.93  4973.8 1066.75
    4992 1066.22  4992.3 1065.72  4995.8 1065.72    4996 1066.22  4999.5 1066.69
  5004.6 1066.69  5009.9 1068.82  5024.6 1070.19  5060.2 1070.39  5116.5 1073.53
  5249.2 1077.46  5261.5 1077.16  5330.9 1077.93  5381.9 1079.27  5407.4 1080.41
  5502.9 1080.93  5558.4 1082.45  5575.9 1083.31    5659 1083.44  5667.9 1084.05
#Mann= 3 ,-1 , 0
  4832.5     .05       0    4992     .03       0    4996     .05       0
Bank Sta=4992,4996
XS Rating Curve= 0 ,0
Exp/Cntr=0.3,0.1

Type RM Length L Ch R = 1 ,9654    ,476,476,476
BEGIN DESCRIPTION:
MOLASSES CREEK 20.0
END DESCRIPTION:
XS GIS Cut Line= 3
      2857768.35     10211859.08       2857311.5       10211642.
      2856674.57     10211572.62
#Sta/Elev= 30
  4494.2  1100.9  4562.2 1097.47  4567.7  1096.3  4607.6 1095.33  4613.2 1094.04
  4635.9 1094.07  4664.2 1091.54  4732.3 1089.34  4762.9 1086.34    4795 1085.09
  4840.4 1079.96  4896.9 1068.01  4919.6 1065.41  4987.8 1060.94  4992.9 1059.31
  4993.2 1058.81  4996.9 1059.31  5015.9 1063.12    5026 1063.41  5056.1 1070.32
  5066.2 1070.99  5186.9 1073.57  5227.2 1075.58  5247.3 1075.16  5317.8 1078.71
  5398.2 1078.91  5518.9 1084.15  5559.1 1083.67  5609.4 1086.15  5640.7 1086.22
#Mann= 3 ,-1 , 0
  4494.2     .05       0  4992.9     .03       0  4996.9     .05       0
Bank Sta=4992.9,4996.9
XS Rating Curve= 0 ,0
Exp/Cntr=0.3,0.1

Type RM Length L Ch R = 1 ,9178    ,479,479,479
BEGIN DESCRIPTION:
MOLASSES CREEK 19.0
END DESCRIPTION:
XS GIS Cut Line= 3
      2857705.64     10211153.12       2857430.5       10211186.
      2857255.67     10211153.11
#Sta/Elev= 30
  4722.9 1077.33  4725.4 1077.33    4743 1073.25  4753.1 1070.74  4761.5 1067.77
  4766.6 1068.27  4776.8 1064.79  4793.4  1060.2  4813.5 1057.32  4833.6 1056.43
  4873.9  1056.6  4914.2  1055.7  4931.4  1053.7  4936.5 1054.07  4954.5 1052.98
  4992.8 1049.27    4993 1048.77  4996.5 1048.77  4996.8 1049.27  4999.9 1050.31
    5005 1050.31  5011.1 1052.11  5015.1 1053.29  5035.4  1055.9  5041.6 1057.19
  5086.3 1061.94  5137.2 1065.25  5151.6 1065.56  5157.5 1066.75  5177.9 1067.22
#Mann= 5 ,-1 , 0
  4722.9     .05       0  4776.8     .12       0  4992.8     .07       0
  4996.8     .12       0  5011.1     .05       0
Bank Sta=4992.8,4996.8
XS Rating Curve= 0 ,0
Exp/Cntr=0.3,0.1

Type RM Length L Ch R = 1 ,8699    ,466,466,466
BEGIN DESCRIPTION:
MOLASSES CREEK 18.0
END DESCRIPTION:
XS GIS Cut Line= 3
       2858005.7     10210803.11      2857602.25       10210751.
      2857255.66     10210903.12
#Sta/Elev= 30
  4593.2 1165.79  4595.7 1165.79  4603.3 1161.67  4623.5 1155.27  4630.4 1150.49
  4635.4 1150.73  4653.7 1142.48  4663.8 1136.47  4697.8 1122.71  4704.1 1120.16
  4709.7 1115.16  4744.5 1101.73  4764.6 1091.19  4774.7 1087.85  4789.1 1087.62
  4793.8 1085.62  4875.5 1065.78  4942.8 1054.89  4947.8 1054.96  4986.5 1044.24
  4993.2 1044.04  4993.7 1044.03    4994 1043.53  4997.7 1044.03  5015.2  1047.8
  5038.5 1048.81  5203.7 1053.01  5241.8 1052.02  5323.9 1057.81  5378.5 1059.62
#Mann= 6 ,-1 , 0
  4593.2     .12       0  4697.8     .05       0  4793.8     .12       0
  4993.2     .05       0  4993.7     .05       0  4997.7     .05       0
Bank Sta=4993.7,4997.7
XS Rating Curve= 0 ,0
Exp/Cntr=0.3,0.1

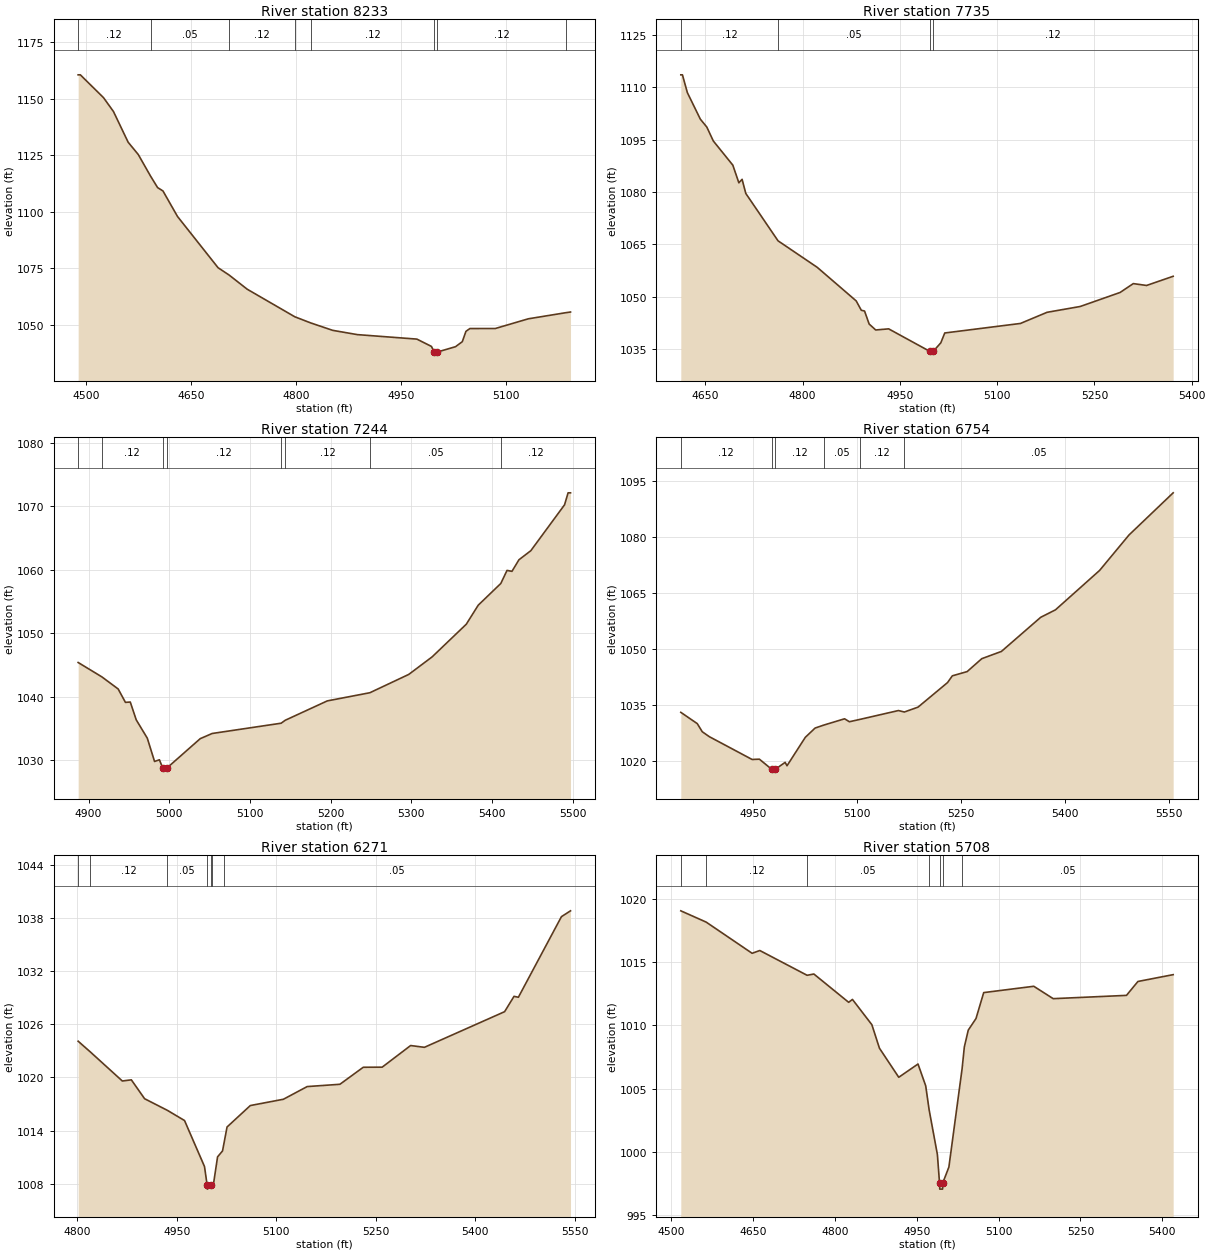
Type RM Length L Ch R = 1 ,8233    ,498,498,498
BEGIN DESCRIPTION:
MOLASSES CREEK 17.0
END DESCRIPTION:
XS GIS Cut Line= 3
      2858005.65     10210753.07        2857693.       10210348.
       2857505.7     10210303.12
#Sta/Elev= 30
  4488.3 1160.52  4491.4 1160.52  4524.5 1150.45  4538.8  1144.3  4559.8 1130.73
  4574.3 1125.28  4591.8 1115.78  4601.9 1110.68  4609.6 1109.19  4630.4 1097.91
  4688.4 1075.26  4704.3 1071.99  4730.1 1065.75  4798.2 1053.56    4821 1050.84
  4852.4 1047.56  4887.7 1045.67  4972.8 1043.69  4993.6 1040.47  4997.7 1037.99
    4998 1037.49  5002.2 1037.99  5028.1 1040.33  5037.8 1042.55    5043 1047.12
  5048.7 1048.36    5085 1048.37  5132.2 1052.66    5186 1055.37  5192.6 1055.66
#Mann= 8 ,-1 , 0
  4488.3     .12       0  4591.8     .05       0  4704.3     .12       0
  4798.2     .05       0    4821     .12       0  4997.7     .07       0
  5002.2     .12       0    5186     .05       0
Bank Sta=4997.7,5002.2
XS Rating Curve= 0 ,0
Exp/Cntr=0.3,0.1

Type RM Length L Ch R = 1 ,7735    ,491,491,491
BEGIN DESCRIPTION:
MOLASSES CREEK 16.0
END DESCRIPTION:
XS GIS Cut Line= 3
      2858155.69     10210603.15        2858135.       10210216.
      2858055.67     10209853.07
#Sta/Elev= 30
  4612.3 1113.57  4614.8 1113.57  4622.4 1108.47  4642.4 1100.88  4652.4 1098.61
  4662.4 1094.63  4692.5  1087.7  4701.8 1082.65  4706.8 1083.64  4712.5  1079.6
  4762.2 1066.03  4822.6 1058.44  4882.7 1048.82  4890.6 1046.14  4895.6 1045.92
  4902.7  1042.2  4912.8 1040.49  4932.8 1040.81  4996.3 1034.36  4996.7 1033.86
  5001.5 1034.36  5013.2 1036.81  5019.3 1039.63    5136 1042.36    5177 1045.55
  5228.2 1047.22  5289.6 1051.23    5310 1053.77  5330.5 1053.24  5371.5 1055.87
#Mann= 4 ,-1 , 0
  4612.3     .12       0  4762.2     .05       0  4996.3     .07       0
  5001.5     .12       0
Bank Sta=4996.3,5001.5
XS Rating Curve= 0 ,0
Exp/Cntr=0.3,0.1

Type RM Length L Ch R = 1 ,7244    ,490,490,490
BEGIN DESCRIPTION:
MOLASSES CREEK 15.0
END DESCRIPTION:
XS GIS Cut Line= 3
      2858655.66     10210153.08      2858593.25       10210059.
       2858305.7     10209653.14
#Sta/Elev= 30
  4887.1 1045.38  4916.5 1043.11  4936.7  1041.2  4945.7 1039.09  4951.7 1039.14
  4959.1 1036.33  4972.8 1033.44  4981.8 1029.76  4987.8 1030.03  4991.9 1028.74
  4992.3 1028.24  4997.2 1028.74  5038.4 1033.36  5053.2 1034.18  5138.7  1035.8
  5143.7 1036.26  5195.9 1039.32  5248.7 1040.61  5296.9  1043.5  5325.9 1046.27
  5368.2 1051.42    5383 1054.42    5411 1057.85  5418.7 1059.91  5424.8 1059.76
  5433.5 1061.59  5448.2 1063.02    5490 1070.26  5494.4 1072.15  5497.4 1072.15
#Mann= 8 ,-1 , 0
  4887.1     .05       0  4916.5     .12       0  4991.9     .07       0
  4997.2     .12       0  5138.7     .05       0  5143.7     .12       0
  5248.7     .05       0    5411     .12       0
Bank Sta=4991.9,4997.2
XS Rating Curve= 0 ,0
Exp/Cntr=0.3,0.1

Type RM Length L Ch R = 1 ,6754    ,483,483,483
BEGIN DESCRIPTION:
MOLASSES CREEK 14.0
END DESCRIPTION:
XS GIS Cut Line= 3
      2858955.68     10209953.14      2858991.25       10209803.
      2858605.68     10209403.11
#Sta/Elev= 30
  4845.7 1032.98  4869.4 1029.96  4876.6 1027.79  4886.8 1026.46  4948.5 1020.35
    4959 1020.43  4976.7 1017.73  4977.1 1017.23    4982 1017.73  4996.1 1019.58
  4998.8 1018.67  5025.2 1026.29  5039.3 1028.77  5051.9 1029.57  5081.8 1031.25
  5088.7 1030.46  5103.7 1031.08  5159.4 1033.46    5168 1033.07  5187.7 1034.38
  5230.2 1040.95  5237.1 1042.76  5258.5  1043.9  5279.6 1047.36  5307.9  1049.3
  5364.5 1058.44  5385.8 1060.44  5449.4 1070.99  5491.8 1080.49  5555.5 1091.79
#Mann= 6 ,-1 , 0
  4845.7     .12       0  4976.7     .07       0    4982     .12       0
  5051.9     .05       0  5103.7     .12       0    5168     .05       0
Bank Sta=4976.7,4982
XS Rating Curve= 0 ,0
Exp/Cntr=0.3,0.1

Type RM Length L Ch R = 1 ,6271    ,563,563,563
BEGIN DESCRIPTION:
MOLASSES CREEK 13.0
END DESCRIPTION:
XS GIS Cut Line= 3
      2859405.69     10209803.07      2859420.25       10209605.
      2859005.66     10209253.09
#Sta/Elev= 30
  4801.4 1024.09  4819.6 1022.89    4868  1019.6  4881.6 1019.73  4901.6  1017.6
  4935.9 1016.29  4961.8 1015.14  4991.9 1009.95  4995.8  1007.9  4996.2  1007.4
  5001.1  1007.9  5002.5  1007.9  5005.3  1007.9  5011.6 1011.04  5019.1 1011.71
  5021.2 1012.54  5025.9 1014.41    5061 1016.83  5110.9 1017.54  5146.7 1018.97
  5196.1 1019.23  5231.3 1021.15  5259.8 1021.16  5302.7  1023.6  5323.5  1023.4
  5444.4 1027.42  5458.6 1029.15  5465.2 1029.05  5530.1 1038.14  5543.8  1038.8
#Mann= 7 ,-1 , 0
  4801.4     .05       0  4819.6     .12       0  4935.9     .05       0
  4995.8     .05       0  5001.1     .05       0  5002.5     .12       0
  5021.2     .05       0
Bank Sta=4995.8,5001.1
XS Rating Curve= 0 ,0
Exp/Cntr=0.3,0.1

Type RM Length L Ch R = 1 ,5708    ,895,895,895
BEGIN DESCRIPTION:
Mapping XS 777bad88
END DESCRIPTION:
XS GIS Cut Line= 2
      2860237.91     10209685.79       2859612.9     10209034.74
#Sta/Elev= 30
  4517.4 1019.06  4563.8 1018.17  4648.1  1015.7  4662.2 1015.92  4748.9 1013.96
  4761.3 1014.06  4825.1 1011.82    4832 1012.05  4867.6 1010.05  4881.5 1008.19
  4916.9 1005.89  4952.2 1006.94  4966.3 1005.21  4972.6 1003.31  4987.7  999.78
  4991.6  997.54  4992.1  997.04  4997.2  997.04  4997.7  997.54  5008.8  998.79
    5033 1006.57  5037.1 1008.29  5044.3 1009.62  5058.5 1010.54  5072.6 1012.59
  5164.4 1013.09    5200 1012.11  5334.3 1012.37  5355.3 1013.47  5419.9 1014.01
#Mann= 7 ,-1 , 0
  4517.4     .05       0  4563.8     .12       0  4748.9     .05       0
  4972.6     .12       0  4991.6     .07       0  4997.7     .12       0
    5033     .05       0
Bank Sta=4991.6,4997.7
XS Rating Curve= 0 ,0
Exp/Cntr=0.3,0.1