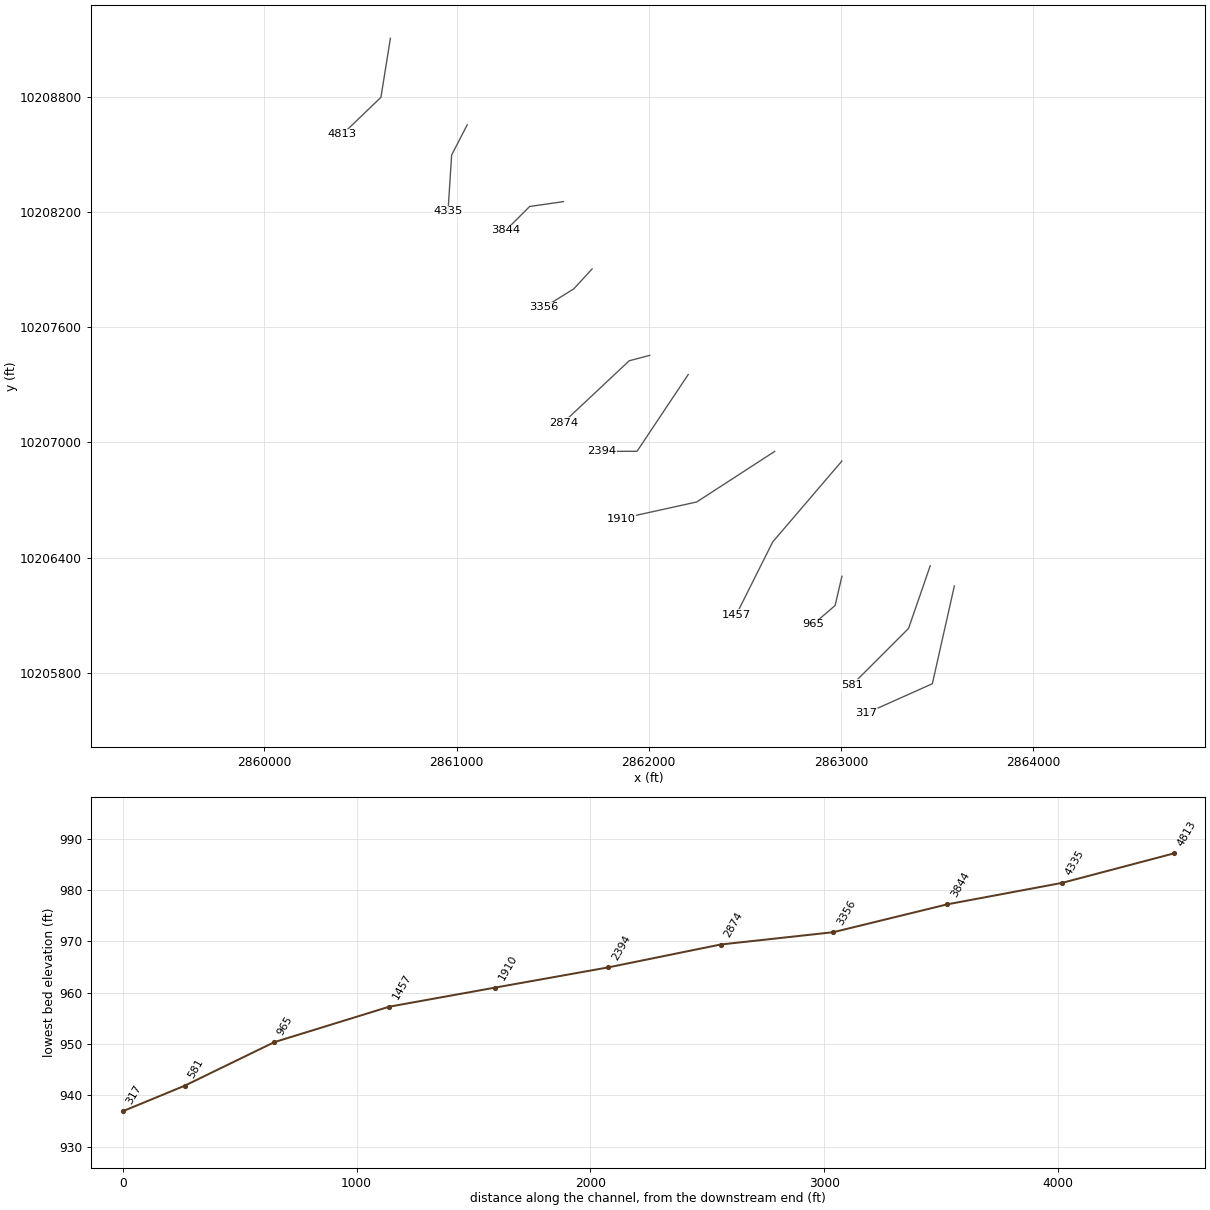
HEC-RAS study MOLASSES CREEK.prj: MOLASSES CREEK Base Level Engineering

--- MOLASSES CREEK.g01 (geometry) --- (continued)

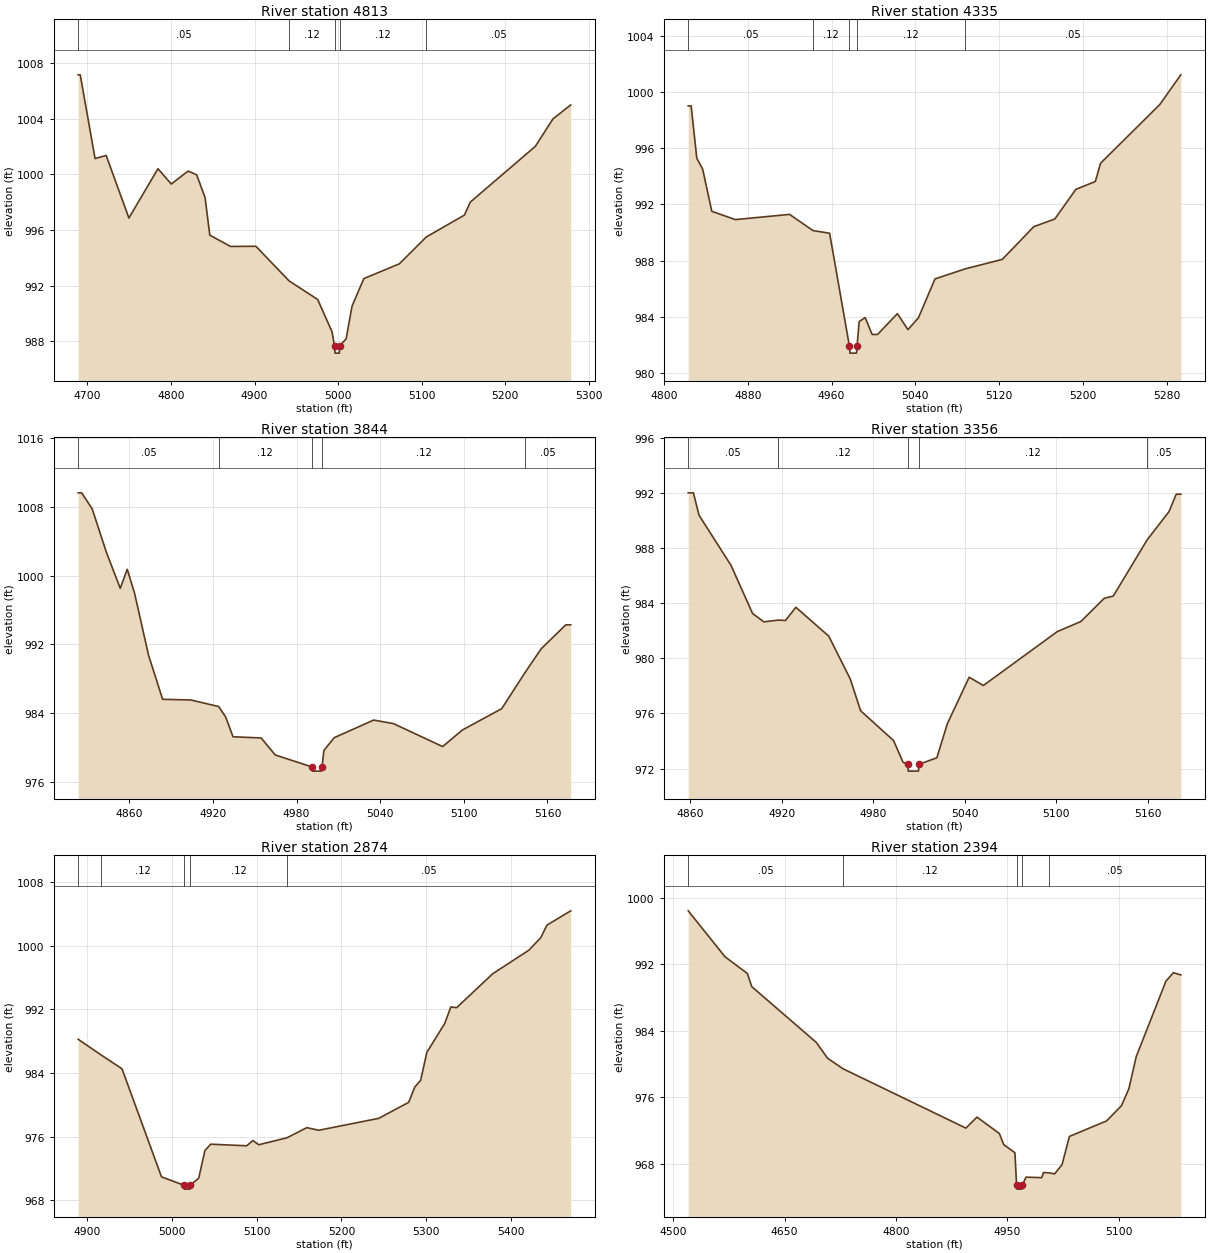
Type RM Length L Ch R = 1 ,4813    ,478,478,478
BEGIN DESCRIPTION:
MOLASSES CREEK 10.0
END DESCRIPTION:
XS GIS Cut Line= 3
      2860655.68     10209103.09       2860606.5       10208796.
      2860405.72     10208603.14
#Sta/Elev= 30
    4689 1007.14  4691.5 1007.14  4709.2 1001.13  4722.5 1001.35  4749.7  996.86
  4784.5  1000.4  4800.4   999.3  4820.6 1000.23  4830.8  999.96  4840.9  998.32
  4846.5  995.63  4871.3  994.82  4901.7  994.83  4941.3  992.35  4975.6  991.01
  4992.8  988.69  4995.8  987.66  4996.3  987.16  5001.5  987.16    5002  987.66
  5009.7   988.2  5016.7  990.53  5030.8  992.51  5073.3  993.57  5105.6   995.5
  5151.2  997.07  5158.2     998  5236.1 1002.01  5257.2 1003.98  5278.4 1004.98
#Mann= 5 ,-1 , 0
    4689     .05       0  4941.3     .12       0  4995.8     .07       0
    5002     .12       0  5105.6     .05       0
Bank Sta=4995.8,5002
XS Rating Curve= 0 ,0
Exp/Cntr=0.3,0.1

Type RM Length L Ch R = 1 ,4335    ,491,491,491
BEGIN DESCRIPTION:
MOLASSES CREEK 9.0
END DESCRIPTION:
XS GIS Cut Line= 3
      2861055.66     10208653.07       2860974.5       10208496.
      2860955.68      10208203.1
#Sta/Elev= 30
  4823.2  999.01    4826  999.01  4831.4  995.28    4837  994.51  4845.7  991.51
  4868.2  990.92    4920  991.29  4942.3  990.14  4958.2  989.95  4977.1  981.92
  4977.6  981.42  4983.9  981.42  4984.4  981.92  4986.4  983.66  4992.1  983.95
  4998.8  982.75    5004  982.75  5022.9  984.23    5033  983.09    5043  983.93
  5058.8   986.7  5087.9  987.42  5123.1  988.09  5153.2  990.42  5173.2  990.96
  5193.3  993.07  5211.9  993.63  5216.9  994.93  5273.5  999.11  5293.5 1001.22
#Mann= 5 ,-1 , 0
  4823.2     .05       0  4942.3     .12       0  4977.1     .07       0
  4984.4     .12       0  5087.9     .05       0
Bank Sta=4977.1,4984.4
XS Rating Curve= 0 ,0
Exp/Cntr=0.3,0.1

Type RM Length L Ch R = 1 ,3844    ,488,488,488
BEGIN DESCRIPTION:
MOLASSES CREEK 8.0
END DESCRIPTION:
XS GIS Cut Line= 3
      2861555.66     10208253.11      2861380.75       10208228.
      2861255.72     10208103.14
#Sta/Elev= 30
  4823.3 1009.63  4825.8 1009.63  4833.4 1007.75  4843.5 1002.73  4853.5  998.51
  4858.5 1000.73  4863.7  997.99  4873.8  990.73  4883.9   985.6  4904.1  985.52
  4924.1  984.76  4929.1  983.55  4934.4  981.24  4954.6   981.1  4964.7  979.12
  4990.8  977.74  4991.3  977.24  4997.8  977.24  4998.3  977.74  4999.6  979.64
    5007  981.13  5035.3  983.18  5049.5  982.77  5084.8   980.1    5099  982.03
  5127.2  984.51  5143.8  988.68  5155.5  991.48  5173.2  994.27  5176.7  994.27
#Mann= 5 ,-1 , 0
  4823.3     .05       0  4924.1     .12       0  4990.8     .07       0
  4998.3     .12       0  5143.8     .05       0
Bank Sta=4990.8,4998.3
XS Rating Curve= 0 ,0
Exp/Cntr=0.3,0.1

Type RM Length L Ch R = 1 ,3356    ,482,482,482
BEGIN DESCRIPTION:
MOLASSES CREEK 7.0
END DESCRIPTION:
XS GIS Cut Line= 3
      2861705.68     10207903.11        2861610.       10207799.
      2861455.67      10207703.1
#Sta/Elev= 30
  4858.6  992.02    4862  992.02  4865.7  990.39  4886.7  986.75  4900.8  983.26
  4908.2  982.65  4917.7  982.78  4922.4  982.75  4929.2  983.71  4950.8  981.61
  4964.9   978.5  4971.7  976.19  4993.3  974.03  4999.5  972.46  5002.5  972.31
    5003  971.81  5009.6  971.81  5010.1  972.31  5021.7  972.78  5028.6  975.26
  5042.9  978.63  5052.2  978.03  5100.8  981.95  5116.1  982.67  5131.5  984.36
  5137.4  984.52  5159.6   988.6    5174  990.66  5178.7  991.92  5181.7  991.92
#Mann= 5 ,-1 , 0
  4858.6     .05       0  4917.7     .12       0  5002.5     .07       0
  5010.1     .12       0  5159.6     .05       0
Bank Sta=5002.5,5010.1
XS Rating Curve= 0 ,0
Exp/Cntr=0.3,0.1

Type RM Length L Ch R = 1 ,2874    ,480,480,480
BEGIN DESCRIPTION:
MOLASSES CREEK 6.0
END DESCRIPTION:
XS GIS Cut Line= 3
      2862005.72     10207453.12      2861898.75       10207425.
      2861555.71     10207103.13
#Sta/Elev= 30
  4889.4  988.25  4916.3  986.29  4941.1  984.54  4987.7  970.95    5014  969.91
  5014.5  969.41  5021.2  969.41  5021.7  969.91  5031.6  970.79  5038.9  974.26
  5045.7  975.06  5088.2  974.86  5095.5  975.52  5102.4  974.99  5135.6  975.86
  5159.1  977.14  5173.2  976.81    5244  978.31  5279.2  980.32  5286.5  982.25
  5293.4   983.1  5300.7  986.61  5321.7  990.22    5329  992.31  5335.9  992.23
  5378.4  996.49  5420.9  999.44    5435 1001.01  5442.3  1002.6  5470.4  1004.4
#Mann= 5 ,-1 , 0
  4889.4     .05       0  4916.3     .12       0    5014     .07       0
  5021.7     .12       0  5135.6     .05       0
Bank Sta=5014,5021.7
XS Rating Curve= 0 ,0
Exp/Cntr=0.3,0.1

Type RM Length L Ch R = 1 ,2394    ,484,484,484
BEGIN DESCRIPTION:
MOLASSES CREEK 5.0
END DESCRIPTION:
XS GIS Cut Line= 3
      2862205.67     10207353.08       2861939.5       10206954.
       2861755.7     10206953.11
#Sta/Elev= 30
  4520.3  998.43  4569.8  992.91  4599.9   990.9  4605.9  989.31    4693  982.59
    4708   980.7  4728.9  979.43  4894.3   972.3  4909.3  973.62  4939.4  971.65
  4945.4   970.3  4960.4  969.34  4962.6  965.46  4963.1  964.96  4969.8  964.96
  4970.3  965.46  4975.4   966.4  4996.5  966.34  4998.9  966.96  5006.4  966.92
  5013.8  966.79  5023.8   967.9  5033.8   971.3  5083.8  973.16  5103.8  974.98
  5113.8  977.01  5123.8   980.9  5163.8  989.97  5173.8  990.99  5183.8  990.72
#Mann= 5 ,-1 , 0
  4520.3     .05       0  4728.9     .12       0  4962.6     .07       0
  4970.3     .12       0  5006.4     .05       0
Bank Sta=4962.6,4970.3
XS Rating Curve= 0 ,0
Exp/Cntr=0.3,0.1

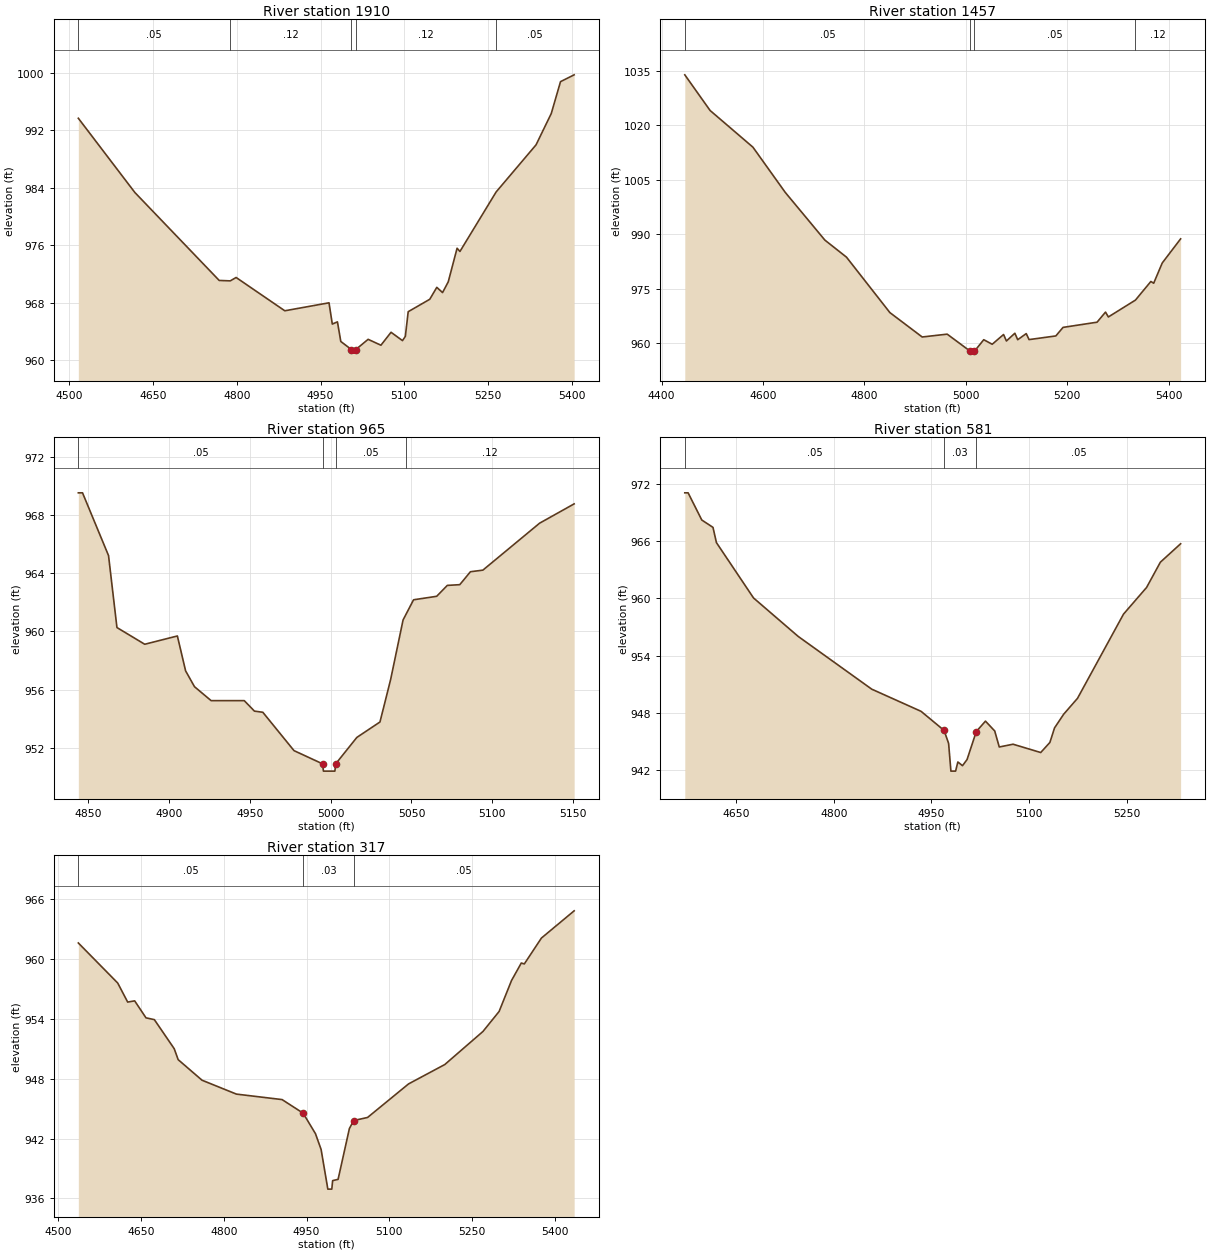
Type RM Length L Ch R = 1 ,1910    ,453,453,453
BEGIN DESCRIPTION:
MOLASSES CREEK 4.0
END DESCRIPTION:
XS GIS Cut Line= 3
      2862655.65     10206953.09        2862250.       10206690.
      2861855.66     10206603.11
#Sta/Elev= 30
  4516.5  993.69  4617.7  983.36  4768.6  971.13  4788.3  971.07  4798.9  971.54
    4886  966.91  4965.1  968.02    4971  965.06  4980.2  965.37  4986.2  962.64
  5005.2  961.52  5005.7  961.02  5013.1  961.52  5035.1  962.94    5058  962.12
  5076.1  963.92  5096.6  962.76  5101.7  963.35  5106.8  966.78  5145.4  968.51
    5158  970.17  5168.3  969.44  5178.5  970.94  5194.3  975.61  5199.4  975.16
  5264.2  983.44  5335.6  989.99  5362.8  994.34  5379.4  998.78  5403.8  999.73
#Mann= 5 ,-1 , 0
  4516.5     .05       0  4788.3     .12       0  5005.2     .07       0
  5013.1     .12       0  5264.2     .05       0
Bank Sta=5005.2,5013.1
XS Rating Curve= 0 ,0
Exp/Cntr=0.3,0.1

Type RM Length L Ch R = 1 ,1457    ,492,492,492
BEGIN DESCRIPTION:
MOLASSES CREEK 3.0
END DESCRIPTION:
XS GIS Cut Line= 3
      2863005.66     10206903.08       2862645.5       10206482.
      2862455.67     10206103.09
#Sta/Elev= 30
  4445.9 1033.86  4495.8 1024.05  4580.3 1013.95    4644 1001.52  4722.2  988.39
  4764.8   983.7  4850.4  968.45  4914.1  961.74  4963.4  962.52  5009.1   957.8
  5009.6   957.3  5017.1   957.8  5035.5  960.99  5052.2  959.74  5074.6  962.42
  5080.2  960.64  5096.9  962.77  5102.5  960.99  5119.3  962.67  5124.9  961.02
  5177.7  962.03  5191.9  964.38    5259  965.81  5275.7  968.59  5281.3  967.25
  5334.7  971.89  5365.1  977.01  5370.7  976.53  5387.5  982.09  5423.8  988.74
#Mann= 4 ,-1 , 0
  4445.9     .05       0  5009.1     .05       0  5017.1     .05       0
  5334.7     .12       0
Bank Sta=5009.1,5017.1
XS Rating Curve= 0 ,0
Exp/Cntr=0.3,0.1

Type RM Length L Ch R = 1 ,965     ,384,384,384
BEGIN DESCRIPTION:
MOLASSES CREEK 2.0
END DESCRIPTION:
XS GIS Cut Line= 3
      2863005.69     10206303.13      2862970.25       10206151.
      2862855.68     10206053.11
#Sta/Elev= 30
  4843.8  969.54  4846.4  969.54  4862.5  965.22  4867.7  960.27  4884.9  959.12
  4905.1  959.69  4910.2  957.29  4915.7   956.2    4926  955.24  4946.5  955.24
  4952.8  954.52    4958  954.44  4977.3   951.8    4995  950.89  4995.5  950.39
  5002.6  950.39  5003.1  950.89  5016.2  952.71  5030.5  953.77  5037.1  956.69
  5044.8  960.79  5046.9  961.24  5051.3  962.18  5065.6  962.42  5072.2  963.17
  5079.9  963.22  5086.5  964.11  5094.2  964.22  5129.3  967.45  5150.7  968.78
#Mann= 4 ,-1 , 0
  4843.8     .05       0    4995     .03       0  5003.1     .05       0
  5046.9     .12       0
Bank Sta=4995,5003.1
XS Rating Curve= 0 ,0
Exp/Cntr=0.3,0.1

Type RM Length L Ch R = 1 ,581     ,264,264,264
BEGIN DESCRIPTION:
Mapping XS 58924902
END DESCRIPTION:
XS GIS Cut Line= 3
      2863465.31     10206357.74      2863352.42     10206031.76
      2863057.74     10205737.09
#Sta/Elev= 30
  4571.2  971.06  4576.3  971.06  4597.3  968.21  4614.5  967.44  4619.8  965.84
  4676.8  960.04  4745.4  956.01  4858.4  950.48  4934.1  948.16  4969.5  946.16
  4976.5  944.79    4980  941.89  4987.2  941.89  4990.7  942.85  4997.8  942.46
  5004.8   943.1    5019  946.04  5033.1  947.13  5047.3   946.1  5054.3  944.42
  5075.5  944.71    5118  943.84  5132.1   944.9  5139.2  946.42  5153.3  947.86
  5174.5  949.52  5245.2  958.35  5280.6  961.14  5301.8  963.79  5332.9  965.72
#Mann= 3 , 0 , 0
  4571.2     .05       0  4969.5     .03       0    5019     .05       0
Bank Sta=4969.5,5019
XS Rating Curve= 0 ,0
Exp/Cntr=0.3,0.1

Type RM Length L Ch R = 1 ,317     ,0,0,0
BEGIN DESCRIPTION:
MOLASSES CREEK 1.0
END DESCRIPTION:
XS GIS Cut Line= 3
      2863590.91     10206252.78      2863476.43     10205743.98
      2863131.44     10205589.77
#Sta/Elev= 30
    4536  961.59  4607.4  957.58  4625.5  955.67  4638.2  955.79  4658.7  954.09
  4673.9  953.91  4709.9     951  4717.1   949.9  4760.4  947.84  4822.7  946.45
  4905.6   945.9  4943.8  944.54  4966.2  942.48  4976.4   940.9  4988.6  936.93
  4995.8  936.93  4997.3  937.78  5007.2  937.91  5027.7     943  5035.5   943.8
  5060.7  944.11    5135  947.47  5200.7  949.41  5269.9  952.72  5299.3  954.73
  5321.8  957.83  5339.5  959.58    5345  959.49    5376  962.08  5435.4  964.81
#Mann= 3 , 0 , 0
    4536     .05       0  4943.8     .03       0  5035.5     .05       0
Bank Sta=4943.8,5035.5
XS Rating Curve= 0 ,0
Exp/Cntr=0.3,0.1

Chan Stop Cuts=-1
Use User Specified Reach Order=0
Composite Channel Slope=5