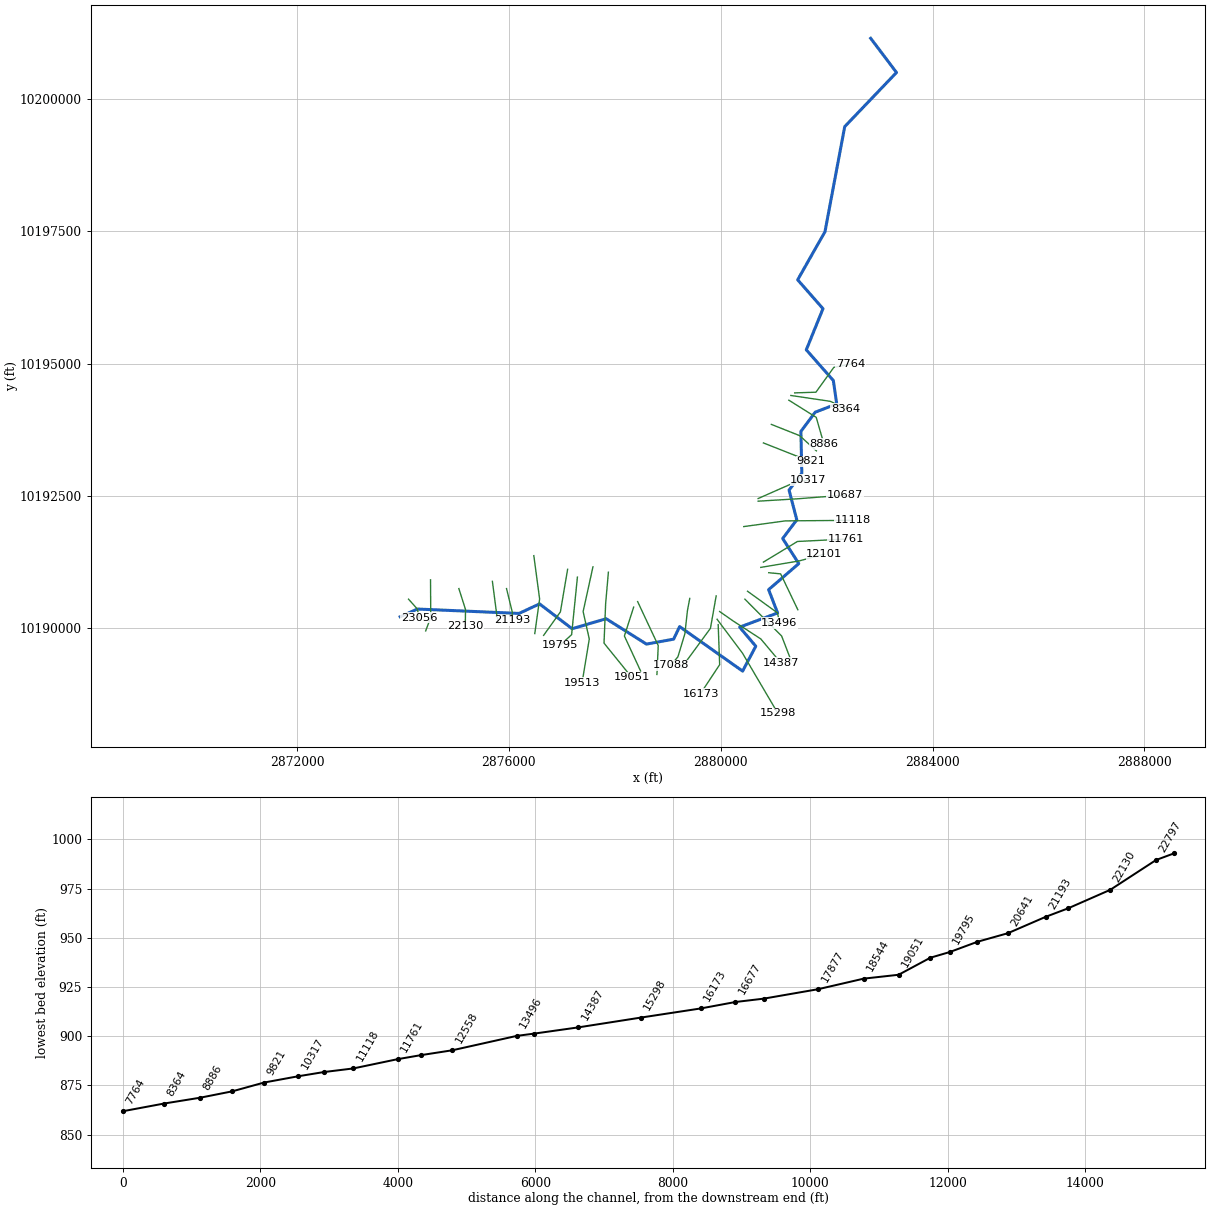
--- MOSS CREEK.prj (project) ---

Proj Title=MOSS CREEK Base Level Engineering
Current Plan=p01
Default Exp/Contr=0.3,0.1
English Units
Geom File=g01
Flow File=f01
Plan File=p01
Y Axis Title=Elevation
X Axis Title(PF)=Main Channel Distance
X Axis Title(XS)=Station
BEGIN DESCRIPTION:
MOSS CREEK
END DESCRIPTION:
DSS Export Rating Curves= 0
DSS Export Rating Curve Sorted= 0
DSS Export Volume Flow Curves= 0
DXF OffsetX= 0
DXF OffsetY= 0
DXF ScaleX= 1
DXF ScaleY= 10

--- MOSS CREEK.p01 (plan) ---

Plan Title=Multiple Run
Short Identifier=Multiple
Geom File=g01
Flow File=f01
Subcritical Flow
K Sum by GR= 0
Std Step Tol= 0.01
Critical Tol= 0.01
Num of Std Step Trials= 20
Max Error Tol= 0.3
Flow Tol Ratio= 0.001
Split Flow NTrial= 30
Split Flow Tol= 0.02
Split Flow Ratio= 0.02
Log Output Level= 0
Friction Slope Method= 1
Unsteady Friction Slope Method= 2
Unsteady Bridges Friction Slope Method= 1
Parabolic Critical Depth
Global Vel Dist=  1 , 1 , 1
Global Log Level= 0
CheckData=True
Encroach Param= -1, 0, 0, 0
BEGIN DESCRIPTION:
Multiple Run
END DESCRIPTION:

--- MOSS CREEK.f01 (steady flow) ---

Flow Title=Multiple
Number of Profiles=7
Profile Names=10-year,25-year,50-year,1pct_min,100-year,1pct_plu,500-year
River Rch & RM= MOSS CREEK,Reach-1,23056
     460     750    1943    1583    2821    5027    4245
River Rch & RM= MOSS CREEK,Reach-1,19051
     768    1297    3057    2316    4459    8582    6606
River Rch & RM= MOSS CREEK,Reach-1,12101
     989    1695    4075    3080    5987   11637    8825
River Rch & RM= MOSS CREEK,Reach-1,9358
    1222    2126    4937    3631    7274   14570   10664
River Rch & RM= MOSS CREEK,Reach-1,4790
    1480    2610    5857    4207    8646   17771   12607
Boundary for River Rch & Prof#=MOSS CREEK,Reach-1,1
Up Type=0
Dn Type=3
Dn Slope=0.005
Boundary for River Rch & Prof#=MOSS CREEK,Reach-1,2
Up Type=0
Dn Type=3
Dn Slope=0.005
Boundary for River Rch & Prof#=MOSS CREEK,Reach-1,3
Up Type=0
Dn Type=3
Dn Slope=0.005
Boundary for River Rch & Prof#=MOSS CREEK,Reach-1,4
Up Type=0
Dn Type=3
Dn Slope=0.005
Boundary for River Rch & Prof#=MOSS CREEK,Reach-1,5
Up Type=0
Dn Type=3
Dn Slope=0.005
Boundary for River Rch & Prof#=MOSS CREEK,Reach-1,6
Up Type=0
Dn Type=3
Dn Slope=0.005
Boundary for River Rch & Prof#=MOSS CREEK,Reach-1,7
Up Type=0
Dn Type=3
Dn Slope=0.005

--- MOSS CREEK.g01 (geometry) ---

Geom Title=Existing Conditions
Program Version=4.10

River Reach=MOSS CREEK      ,Reach-1
Reach XY= 30
      2873948.25       10190221.      2874271.75       10190367.
       2876191.5       10190284.       2876579.5       10190464.
      2877193.25       10189995.      2877836.25       10190184.
      2878597.75       10189705.      2879109.25       10189798.
        2879224.       10190035.        2880413.       10189195.
      2880661.75       10189665.        2880357.       10190025.
       2881073.5       10190293.        2880904.       10190733.
      2881473.75       10191225.       2881169.5       10191698.
      2881435.75       10192052.        2881290.       10192612.
      2881530.75       10192930.      2881513.25       10193720.
      2881783.25       10194083.        2882190.       10194240.
      2882125.25       10194682.      2881615.25       10195261.
      2881930.25       10196038.      2881452.25       10196583.
      2881967.75       10197490.      2882340.75       10199475.
      2883318.25       10200497.       2882831.5       10201142.

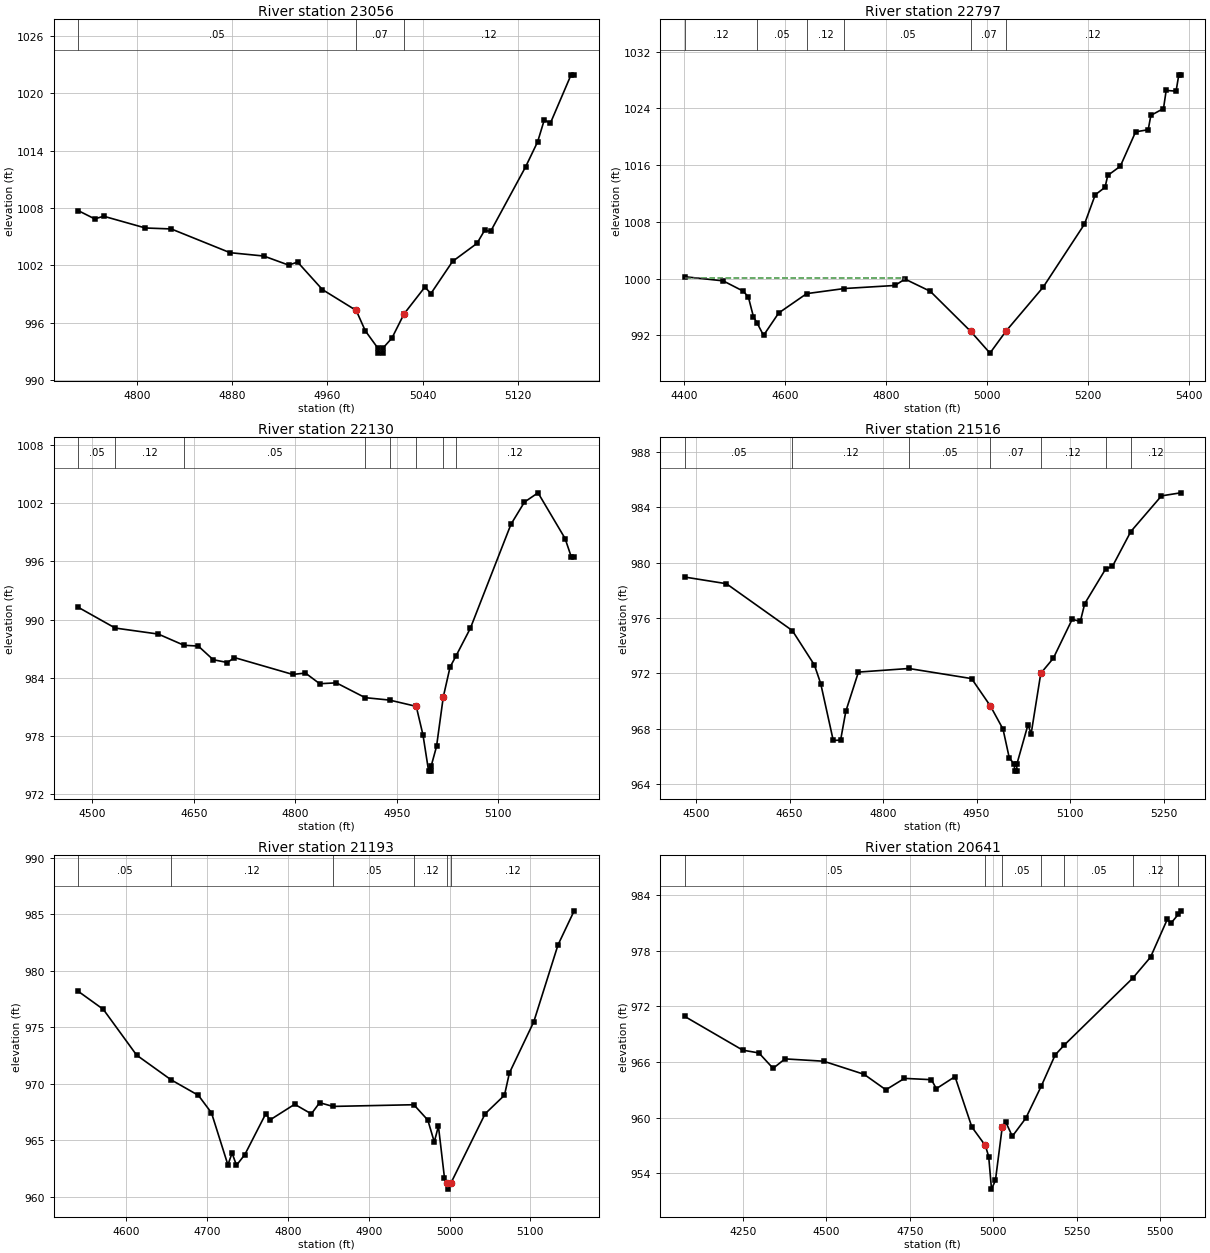
Type RM Length L Ch R = 1 ,23056   ,259,259,259
BEGIN DESCRIPTION:
MOSS CREEK 45.0
END DESCRIPTION:
XS GIS Cut Line= 3
       2874105.7     10190553.09      2874271.75       10190367.
      2874305.69     10190203.08
#Sta/Elev= 30
  4750.6 1007.73  4764.4 1006.87  4771.9 1007.15    4807 1005.92  4828.7 1005.82
  4878.1 1003.34  4906.5 1002.99  4927.4 1002.04  4934.9 1002.36  4955.8  999.48
  4984.2   997.3  4991.8  995.18  5002.5  993.34  5002.8  992.84  5006.3  992.84
  5006.5  993.34  5014.2  994.41  5024.4  996.94  5041.9  999.74    5047  999.07
  5065.2 1002.43  5085.7 1004.31  5092.1 1005.67  5097.2 1005.57  5126.5 1012.29
  5136.7 1014.93  5142.3 1017.22  5147.4 1016.87  5164.8 1021.93  5167.4 1021.93
#Mann= 3 , 0 , 0
  4750.6     .05       0  4984.2     .07       0  5024.4     .12       0
Bank Sta=4984.2,5024.4
XS Rating Curve= 0 ,0
Exp/Cntr=0.3,0.1

Type RM Length L Ch R = 1 ,22797   ,667,667,667
BEGIN DESCRIPTION:
MOSS CREEK 44.0
END DESCRIPTION:
XS GIS Cut Line= 3
      2874520.64       10190919.      2874524.89     10190209.66
      2874429.33     10189954.84
#Sta/Elev= 30
  4401.2 1000.26  4477.1  999.68  4517.1  998.22  4527.1  997.38  4537.1  994.61
  4544.3  993.74  4557.1  991.99  4587.1  995.15  4642.5  997.88  4717.3   998.6
  4817.1  999.03  4837.1  999.93  4887.1  998.21  4967.1  992.56  5005.3  989.49
  5037.1   992.6  5110.5  998.78  5192.3 1007.67  5213.7 1011.82  5233.1 1012.87
  5238.4 1014.54  5263.3 1015.84  5293.6 1020.69  5318.5 1020.99  5323.8 1023.01
  5348.8 1023.98  5354.1 1026.53  5373.7 1026.43    5379 1028.69  5382.7 1028.73
#Mann= 6 ,-1 , 0
  4401.2     .12       0  4544.3     .05       0  4642.5     .12       0
  4717.3     .05       0  4967.1     .07       0  5037.1     .12       0
#XS Ineff= 2 , 0
         4835.23 1000.06
Permanent Ineff=
       F       F
Bank Sta=4967.1,5037.1
XS Rating Curve= 0 ,0
Exp/Cntr=0.3,0.1

Type RM Length L Ch R = 1 ,22130   ,614,614,614
BEGIN DESCRIPTION:
MOSS CREEK 43.0
END DESCRIPTION:
XS GIS Cut Line= 3
       2875055.7     10190753.07      2875181.14     10190358.33
       2875176.9     10190039.75
#Sta/Elev= 30
  4479.2  991.26  4533.7  989.12  4597.3   988.5  4635.4  987.34  4656.5  987.26
  4678.5  985.85  4699.5  985.56    4710  986.07    4796  984.33  4814.9  984.47
  4835.9  983.37  4860.5  983.46  4903.1  981.93  4939.1  981.68  4978.6  981.03
  4988.6  978.07  4996.9  974.34  5000.4  974.34  5000.6  974.84  5008.6  976.89
  5018.6  982.01  5028.6  985.09  5037.4  986.24  5058.6   989.1  5118.6  999.84
  5138.6 1002.14  5158.6 1003.09  5198.6  998.37  5207.8  996.46    5212  996.46
#Mann= 8 ,-1 , 0
  4479.2     .05       0  4533.7     .12       0  4635.4     .05       0
  4903.1     .12       0  4939.1     .05       0  4978.6     .07       0
  5018.6     .05       0  5037.4     .12       0
Bank Sta=4978.6,5018.6
XS Rating Curve= 0 ,0
Exp/Cntr=0.3,0.1

Type RM Length L Ch R = 1 ,21516   ,323,323,323
BEGIN DESCRIPTION:
MOSS CREEK 42.0
END DESCRIPTION:
XS GIS Cut Line= 3
      2875688.74     10190889.25      2875772.93     10190244.98
      2875805.67     10190103.16
#Sta/Elev= 30
    4482  978.96  4548.7  978.48  4654.5  975.09  4689.9   972.6    4700  971.26
  4720.1  967.15  4731.9  967.17  4740.3  969.26  4760.5  972.09  4841.4  972.35
    4942  971.62  4972.3  969.63  4992.4  967.97  5002.5  965.88  5010.6  965.43
  5010.9  964.93  5014.4  964.93  5014.6  965.43  5032.5  968.29  5037.5  967.62
    5053     972  5073.1  973.09  5103.4  975.91  5116.4  975.75  5123.5  977.04
  5157.1  979.55  5167.9  979.73  5197.4  982.25  5246.6  984.83  5277.3  985.05
#Mann= 7 ,-1 , 0
    4482     .05       0  4654.5     .12       0  4841.4     .05       0
  4972.3     .07       0    5053     .12       0  5157.1     .05       0
  5197.4     .12       0
Bank Sta=4972.3,5053
XS Rating Curve= 0 ,0
Exp/Cntr=0.3,0.1

Type RM Length L Ch R = 1 ,21193   ,552,552,552
BEGIN DESCRIPTION:
MOSS CREEK 41.0
END DESCRIPTION:
XS GIS Cut Line= 3
      2875955.68     10190753.12       2876064.5       10190307.
      2876055.69     10190153.15
#Sta/Elev= 30
  4540.8  978.16  4571.7  976.57  4612.9  972.52  4655.4  970.34  4689.3  968.96
  4705.5  967.41  4725.8  962.81    4731  963.85  4736.4  962.77  4746.7  963.71
  4772.7  967.34  4777.8  966.78  4808.4  968.17    4829  967.32  4839.3  968.31
  4855.7  967.98  4955.8  968.13  4973.1  966.77  4981.1  964.83  4986.2  966.24
  4993.7  961.65  4997.4  961.16  4997.7  960.66  5001.4  961.16    5044  967.33
  5067.9  968.97    5074  970.94  5104.1  975.46  5134.1  982.27  5154.1  985.29
#Mann= 6 ,-1 , 0
  4540.8     .05       0  4655.4     .12       0  4855.7     .05       0
  4955.8     .12       0  4997.4     .07       0  5001.4     .12       0
Bank Sta=4997.4,5001.4
XS Rating Curve= 0 ,0
Exp/Cntr=0.3,0.1

Type RM Length L Ch R = 1 ,20641   ,443,443,443
BEGIN DESCRIPTION:
MOSS CREEK 40.0
END DESCRIPTION:
XS GIS Cut Line= 3
      2876470.86     10191375.15      2876580.22     10190557.48
      2876489.08     10189903.86
#Sta/Elev= 30
  4076.5  970.91  4250.1  967.28  4298.5  966.98  4340.9  965.32  4376.6  966.34
  4492.2  966.09  4613.3  964.68  4678.7  963.01  4734.3  964.24  4815.1   964.1
  4829.8  963.13  4885.7  964.43  4936.2     959  4976.5  957.01  4986.6  955.82
    4995  952.31  5006.8  953.25    5027  958.95  5037.1  959.59  5057.3     958
  5097.7  959.95    5144   963.4  5185.6  966.76  5212.9  967.83  5418.1  975.04
  5471.3   977.3  5521.8   981.4  5531.9  980.93  5554.7  981.92  5561.4  982.29
#Mann= 7 ,-1 , 0
  4076.5     .05       0  4976.5     .05       0    5027     .05       0
    5144     .12       0  5212.9     .05       0  5418.1     .12       0
  5554.7     .05       0
Bank Sta=4976.5,5027
XS Rating Curve= 0 ,0
Exp/Cntr=0.3,0.1

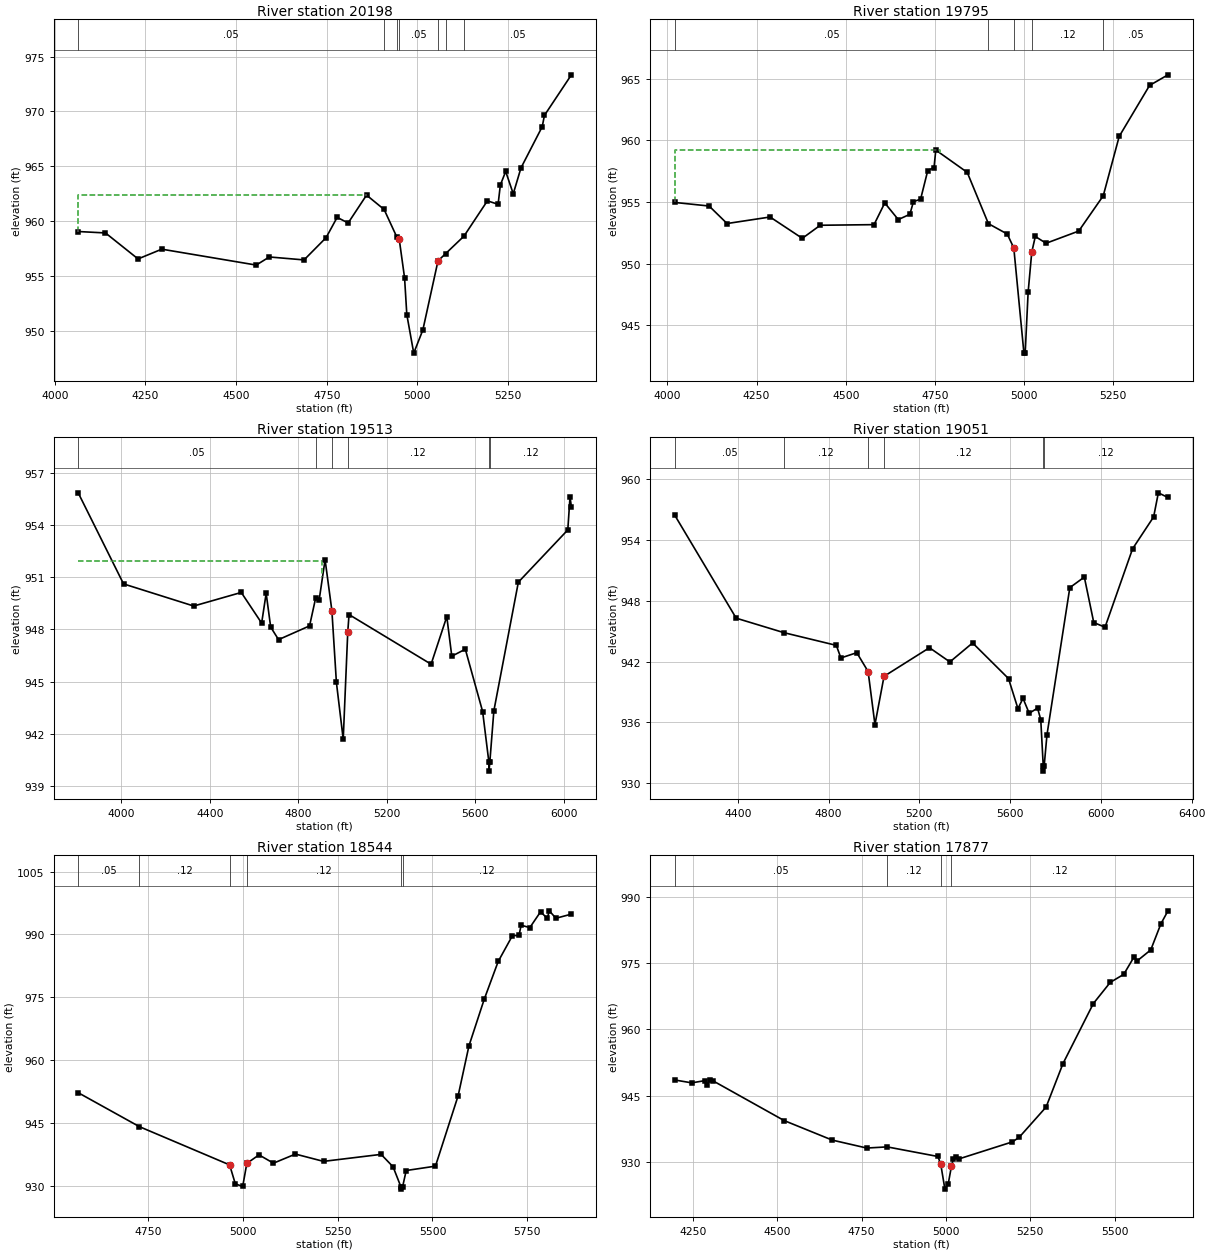
Type RM Length L Ch R = 1 ,20198   ,403,403,403
BEGIN DESCRIPTION:
MOSS CREEK 39.0
END DESCRIPTION:
XS GIS Cut Line= 3
      2877108.86     10191117.34      2876972.58     10190312.97
      2876655.72     10189869.95
#Sta/Elev= 30
  4064.5  959.05  4139.8  958.92  4229.6  956.55    4295  957.44  4555.6  955.99
  4591.7  956.73  4687.5  956.46  4748.3  958.49  4778.8  960.34  4809.2  959.83
  4859.9  962.37  4908.4  961.06  4943.1  958.57  4950.1  958.34  4964.8  954.83
    4971  951.47  4990.1  947.96  5015.2  950.07    5057  956.37  5077.9  957.03
  5128.7  958.63  5193.3  961.85  5222.8  961.53    5229  963.29  5243.7  964.53
  5264.6  962.49  5285.9  964.85  5344.5  968.61  5350.6  969.64    5425  973.34
#Mann= 7 ,-1 , 0
  4064.5     .05       0  4908.4     .12       0  4943.1     .05       0
  4950.1     .05       0    5057     .05       0  5077.9     .12       0
  5128.7     .05       0
#XS Ineff= 2 , 0
         4860.91  962.39
Permanent Ineff=
       F       F
Bank Sta=4950.1,5057
XS Rating Curve= 0 ,0
Exp/Cntr=0.3,0.1

Type RM Length L Ch R = 1 ,19795   ,282,282,282
BEGIN DESCRIPTION:
MOSS CREEK 38.0
END DESCRIPTION:
XS GIS Cut Line= 3
      2877293.77     10190968.95      2877184.39     10189883.01
      2876969.43     10189686.18
#Sta/Elev= 30
  4020.7  954.96    4117  954.67  4167.3  953.25  4287.9  953.78  4378.3  952.05
  4428.6  953.11  4579.4  953.16  4609.5  954.92  4647.4  953.57  4679.9     954
  4689.9  955.02    4710  955.23  4730.1  957.55  4747.6  957.79  4752.6  959.21
  4840.7   957.4  4900.1  953.24  4952.9   952.4  4971.3  951.27  4999.7  942.74
  5003.2  942.74  5011.5  947.68  5021.6  950.92  5031.6   952.2  5061.8  951.65
  5153.4  952.64  5222.1   955.5  5266.9  960.32    5352  964.45  5403.6  965.31
#Mann= 5 ,-1 , 0
  4020.7     .05       0  4900.1     .12       0  4971.3     .05       0
  5021.6     .12       0  5222.1     .05       0
#XS Ineff= 2 , 0
         4764.55  959.25
Permanent Ineff=
       F       F
Bank Sta=4971.3,5021.6
XS Rating Curve= 0 ,0
Exp/Cntr=0.3,0.1

Type RM Length L Ch R = 1 ,19513   ,462,462,462
BEGIN DESCRIPTION:
Mapping XS 7614348f
END DESCRIPTION:
XS GIS Cut Line= 4
      2877587.18     10191163.42       2877401.8     10190318.33
      2877517.93     10189800.83       2877382.5     10188977.04
#Sta/Elev= 30
    3805  955.84  4010.1  950.61  4327.4  949.34  4542.4  950.12  4634.6  948.36
    4655  950.07  4675.5  948.13  4711.1  947.41  4851.3   948.2    4879  949.81
  4894.7  949.69  4921.5     952  4952.2  949.08  4972.7  944.95  5003.5  941.69
    5024  947.84  5029.8  948.85  5400.9     946  5471.9  948.73  5494.5  946.46
  5555.7  946.86    5634  943.28  5662.4  940.36  5662.7  939.86  5666.4  940.36
  5684.7  943.32  5795.5  950.71  6019.1  953.71  6029.2  955.61  6035.4  955.03
#Mann= 6 ,-1 , 0
    3805     .05       0    4879     .12       0  4952.2     .05       0
    5024     .12       0  5662.4     .05       0  5666.4     .12       0
#XS Ineff= 2 , 0
         4909.66  951.95
Permanent Ineff=
       F       F
Bank Sta=4952.2,5024
XS Rating Curve= 0 ,0
Exp/Cntr=0.3,0.1

Type RM Length L Ch R = 1 ,19051   ,507,507,507
BEGIN DESCRIPTION:
Mapping XS 0d2e7cb5
END DESCRIPTION:
XS GIS Cut Line= 4
      2877878.83     10191062.65      2877826.75     10190468.94
      2877796.27     10189723.24      2878319.16     10189077.39
#Sta/Elev= 30
  4122.3  956.41  4392.9  946.27  4603.7  944.84  4834.2  943.59  4854.2  942.35
  4924.3  942.87  4974.3  941.01  5004.4  935.78  5044.4  940.54  5244.6  943.36
  5334.6  941.96  5434.7  943.83  5592.9  940.32  5634.5  937.36  5656.8  938.37
  5684.1   936.9  5720.8  937.41    5735  936.28    5746   931.7  5746.3   931.2
    5750   931.7  5762.4  934.78  5863.1  949.28    5927  950.32  5968.6  945.84
  6018.2  945.38  6139.7  953.11  6232.4  956.25  6253.2  958.62  6295.6  958.16
#Mann= 6 ,-1 , 0
  4122.3     .05       0  4603.7     .12       0  4974.3     .05       0
  5044.4     .12       0    5746     .07       0    5750     .12       0
Bank Sta=4974.3,5044.4
XS Rating Curve= 0 ,0
Exp/Cntr=0.3,0.1

Type RM Length L Ch R = 1 ,18544   ,667,667,667
BEGIN DESCRIPTION:
MOSS CREEK 35.0
END DESCRIPTION:
XS GIS Cut Line= 3
      2878355.67     10190403.07      2878180.92     10189857.83
      2878486.47     10189198.12
#Sta/Elev= 30
  4566.5  952.24  4727.8  944.14  4965.5  935.02 4980.53  930.49 4999.97  929.88
  5010.8  935.37  5042.9  937.41    5081  935.43  5138.9   937.6  5212.9  935.86
  5364.7  937.53  5396.2  934.56  5417.1  929.74  5417.4  929.24  5421.2  929.74
  5430.8  933.68  5507.9  934.72  5567.7  951.53  5596.1   963.4  5636.4  974.53
  5673.2  983.54  5710.7   989.7  5728.1  989.75  5733.6   992.2  5756.5  991.61
    5785  995.41  5802.4   993.8  5807.9  995.62  5825.3  993.85  5866.1  994.83
#Mann= 6 ,-1 , 0
  4566.5     .05       0  4727.8     .12       0  4965.5     .05       0
  5010.8     .12       0  5417.1     .07       0  5421.2     .12       0
Bank Sta=4965.5,5010.8
XS Rating Curve= 0 ,0
Exp/Cntr=0.3,0.1

Type RM Length L Ch R = 1 ,17877   ,789,789,789
BEGIN DESCRIPTION:
MOSS CREEK 34.0
END DESCRIPTION:
XS GIS Cut Line= 3
      2878430.93     10190507.12      2878819.81     10189677.28
       2878795.5     10189132.16
#Sta/Elev= 30
  4196.2  948.53  4246.5  947.88  4286.7   948.4  4292.2  947.38    4300  948.47
  4309.5  948.34  4520.5  939.35  4662.9  934.94  4765.3  933.14  4825.9   933.4
  4976.3  931.23  4984.7  929.47    4997  923.85  5006.8  925.02  5016.4  929.02
  5021.9  930.64  5028.9  931.03  5039.2   930.7  5196.9  934.53  5216.9  935.54
    5297  942.41    5347  952.23  5437.1  965.82  5487.2   970.6  5527.2  972.42
  5557.2  976.29  5567.3  975.48  5607.3  977.95  5637.3  983.84  5658.3  986.78
#Mann= 4 ,-1 , 0
  4196.2     .05       0  4825.9     .12       0  4984.7     .07       0
  5016.4     .12       0
Bank Sta=4984.7,5016.4
XS Rating Curve= 0 ,0
Exp/Cntr=0.3,0.1

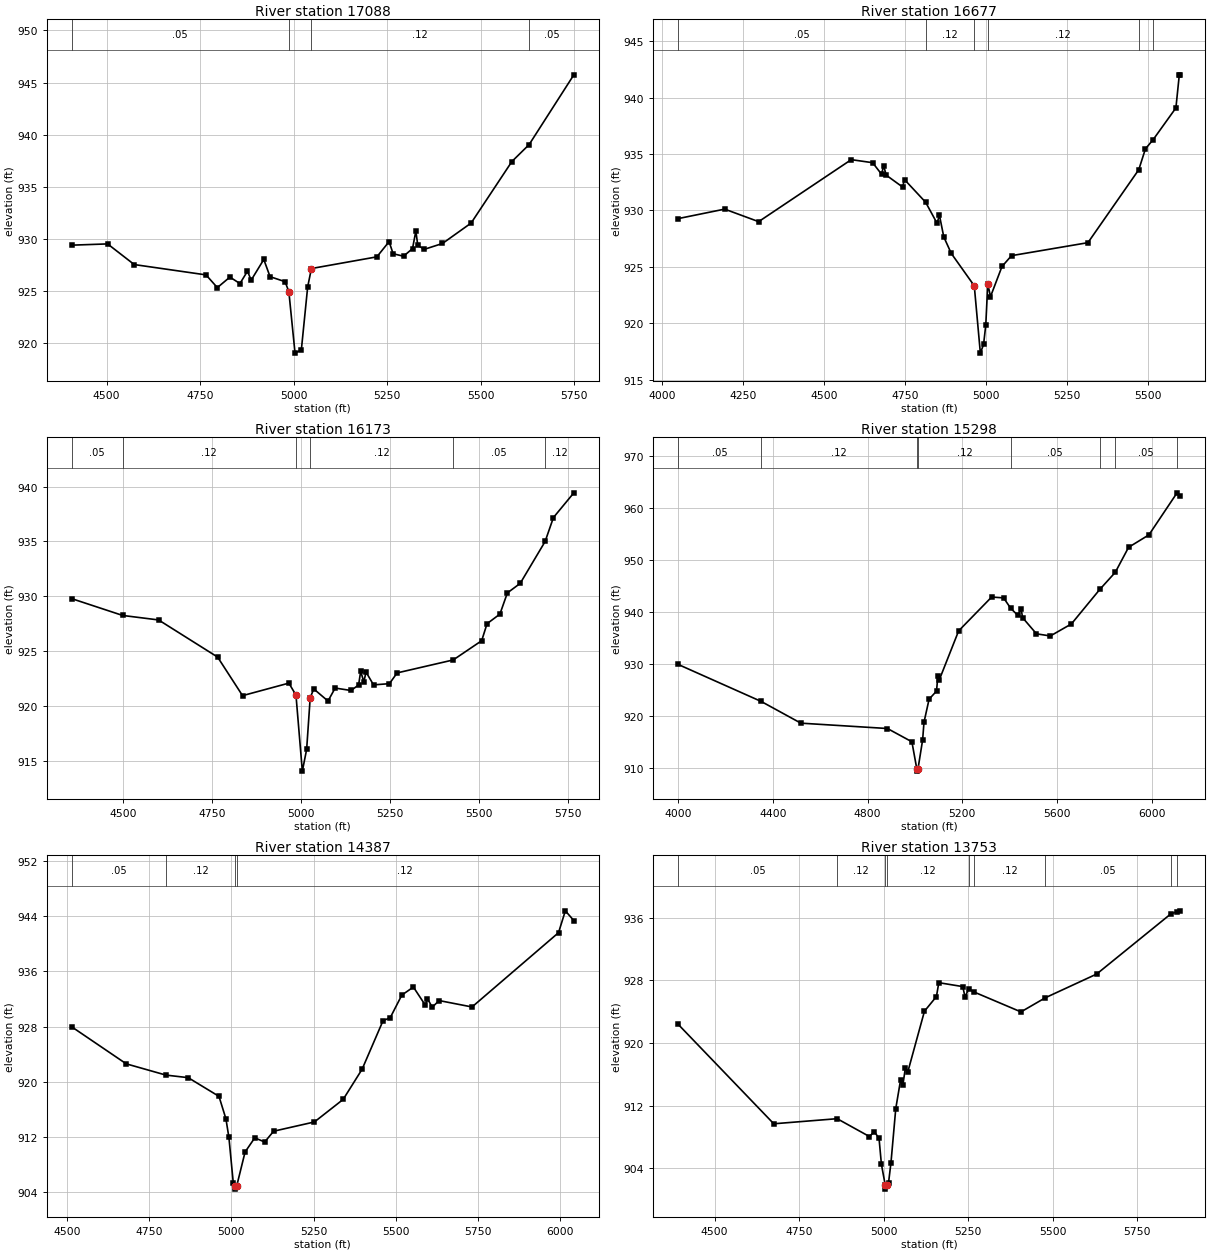
Type RM Length L Ch R = 1 ,17088   ,411,411,411
BEGIN DESCRIPTION:
Mapping XS 4b47ad8d
END DESCRIPTION:
XS GIS Cut Line= 5
      2879414.86     10190567.58      2879371.42     10190337.91
      2879322.81     10189900.41      2879190.87     10189462.91
      2879051.95     10189303.15
#Sta/Elev= 30
  4406.4  929.42  4502.5  929.54  4573.8  927.56  4765.7  926.57  4795.9  925.35
  4829.5  926.36  4856.3  925.74  4876.4  926.92  4886.4  926.07  4920.1  928.05
  4936.8   926.4    4977  925.92  4987.1  924.96  5003.6  919.07 5020.49  919.38
  5037.4  925.42  5047.4  927.18  5222.4   928.3  5255.1  929.76  5265.8   928.6
  5293.6  928.36  5317.7  929.09  5326.6  930.77  5331.8  929.41  5349.1  929.02
  5397.7  929.58  5474.4  931.54  5583.4  937.44  5629.4  939.06    5749  945.75
#Mann= 4 ,-1 , 0
  4406.4     .05       0  4987.1     .05       0  5047.4     .12       0
  5629.4     .05       0
Bank Sta=4987.1,5047.4
XS Rating Curve= 0 ,0
Exp/Cntr=0.3,0.1

Type RM Length L Ch R = 1 ,16677   ,504,504,504
BEGIN DESCRIPTION:
MOSS CREEK 32.0
END DESCRIPTION:
XS GIS Cut Line= 3
      2879913.56     10190614.77      2879805.68     10190003.11
      2879255.66     10189253.07
#Sta/Elev= 30
  4048.7  929.28  4192.5  930.12  4297.4  929.01  4583.5   934.5  4649.5  934.23
  4677.1  933.21  4683.3  933.96  4691.8  933.12  4741.9  932.08  4748.1  932.73
  4813.2  930.73  4848.5  928.87  4855.8  929.59  4869.3  927.66  4892.4   926.2
  4963.5  923.33  4982.3  917.37  4992.2  918.14    4999  919.85  5005.2  923.51
  5013.6  922.37  5049.1  925.04  5078.5     926  5314.6  927.15  5471.6  933.61
  5492.2  935.46    5516  936.27  5586.3  939.08  5596.8  942.01  5599.9  942.01
#Mann= 6 ,-1 , 0
  4048.7     .05       0  4813.2     .12       0  4963.5     .05       0
  5005.2     .12       0  5471.6     .05       0    5516     .12       0
Bank Sta=4963.5,5005.2
XS Rating Curve= 0 ,0
Exp/Cntr=0.3,0.1

Type RM Length L Ch R = 1 ,16173   ,875,875,875
BEGIN DESCRIPTION:
MOSS CREEK 31.0
END DESCRIPTION:
XS GIS Cut Line= 3
      2879951.75     10190073.07      2879979.53     10189316.17
      2879618.42     10188771.03
#Sta/Elev= 30
  4355.5   929.8  4498.8  928.27  4599.8  927.86  4765.7  924.48  4835.8  920.97
  4965.9  922.11  4985.9  921.02  5003.8   914.1  5015.9  916.08  5025.9  920.79
  5035.9  921.58  5075.9  920.48    5096  921.66  5140.6  921.44  5161.9  921.94
  5167.8  923.19  5176.5  922.23  5182.9  923.11  5203.9  921.95  5248.5  922.06
  5270.2  923.04  5427.8  924.22  5507.8  925.97  5522.9  927.52    5559  928.39
    5580  930.32  5616.1  931.19  5686.1     935  5709.4  937.18  5766.8  939.43
#Mann= 6 ,-1 , 0
  4355.5     .05       0  4498.8     .12       0  4985.9     .07       0
  5025.9     .12       0  5427.8     .05       0  5686.1     .12       0
Bank Sta=4985.9,5025.9
XS Rating Curve= 0 ,0
Exp/Cntr=0.3,0.1

Type RM Length L Ch R = 1 ,15298   ,911,911,911
BEGIN DESCRIPTION:
Mapping XS ef059ffa
END DESCRIPTION:
XS GIS Cut Line= 3
      2879930.94     10190173.77      2880410.09     10189534.92
      2881079.62     10188397.05
#Sta/Elev= 30
  4000.9  929.95  4351.1  922.84  4518.8  918.66  4884.1  917.63  4987.2  915.08
  5007.7  909.94  5008.1  909.44  5013.2  909.94  5032.5  915.43  5038.3  918.84
  5059.8  923.27  5091.1  924.82  5096.9  927.74  5103.2  927.03  5184.5   936.4
  5323.7   942.9  5374.2  942.74  5404.2  940.73  5432.8  939.44  5448.4  940.54
  5454.2  938.94  5512.8  935.83  5571.4  935.42  5660.2  937.73  5780.1  944.37
  5845.2  947.64  5901.5  952.46  5987.3  954.85    6106  962.93  6119.7  962.33
#Mann= 8 ,-1 , 0
  4000.9     .05       0  4351.1     .12       0  5007.7     .07       0
  5013.2     .12       0  5404.2     .05       0  5780.1     .12       0
  5845.2     .05       0    6106     .12       0
Bank Sta=5007.7,5013.2
XS Rating Curve= 0 ,0
Exp/Cntr=0.3,0.1

Type RM Length L Ch R = 1 ,14387   ,634,634,634
BEGIN DESCRIPTION:
MOSS CREEK 30.0
END DESCRIPTION:
XS GIS Cut Line= 5
      2879979.57     10190319.61        2880233.     10190142.55
      2880755.68     10189803.11      2881132.31     10189354.36
      2881139.24     10189350.89
#Sta/Elev= 30
    4515  927.98    4681  922.61  4801.6  920.98  4869.1  920.61  4962.7   917.9
  4983.8  914.64  4992.9  911.94  5006.2  905.32  5011.2  904.96  5011.7  904.46
  5016.8  904.96    5042  909.84  5071.4  911.89  5101.6  911.29  5128.7  912.85
  5252.6  914.19  5340.1  917.46  5397.6  921.83  5461.1  928.85  5483.2  929.31
  5518.3  932.57  5553.4  933.74  5589.8   931.1  5596.3  932.05  5610.7  930.81
  5631.5  931.78  5731.6  930.85  5994.4  941.61  6015.2  944.78    6041  943.37
#Mann= 4 ,-1 , 0
    4515     .05       0  4801.6     .12       0  5011.2     .07       0
  5016.8     .12       0
Bank Sta=5011.2,5016.8
XS Rating Curve= 0 ,0
Exp/Cntr=0.3,0.1

Type RM Length L Ch R = 1 ,13753   ,257,257,257
BEGIN DESCRIPTION:
MOSS CREEK 29.0
END DESCRIPTION:
XS GIS Cut Line= 3
      2880455.69     10190553.11      2881149.67     10189857.83
      2881330.23     10189389.06
#Sta/Elev= 30
  4392.3  922.38  4675.1  909.68  4862.5  910.33    4958  908.05  4972.1  908.68
  4986.3  907.83  4993.3  904.52  5004.7  901.84  5005.1  901.34  5010.3  901.84
  5014.5  902.18  5021.6  904.72  5035.8  911.63  5049.9  915.24    5057  914.69
    5064  916.75  5071.1  916.26  5120.6  924.05    5156  925.92    5163  927.69
  5233.7  927.19  5240.8  925.85  5251.1  926.91  5266.6  926.51  5405.9  923.96
  5478.2  925.77  5629.7  928.79    5849  936.47    5866  936.72    5877  936.86
#Mann= 9 ,-1 , 0
  4392.3     .05       0  4862.5     .12       0  5004.7     .07       0
  5010.3     .12       0  5251.1     .05       0  5266.6     .12       0
  5478.2     .05       0    5849     .12       0    5866     .05       0
Bank Sta=5004.7,5010.3
XS Rating Curve= 0 ,0
Exp/Cntr=0.3,0.1

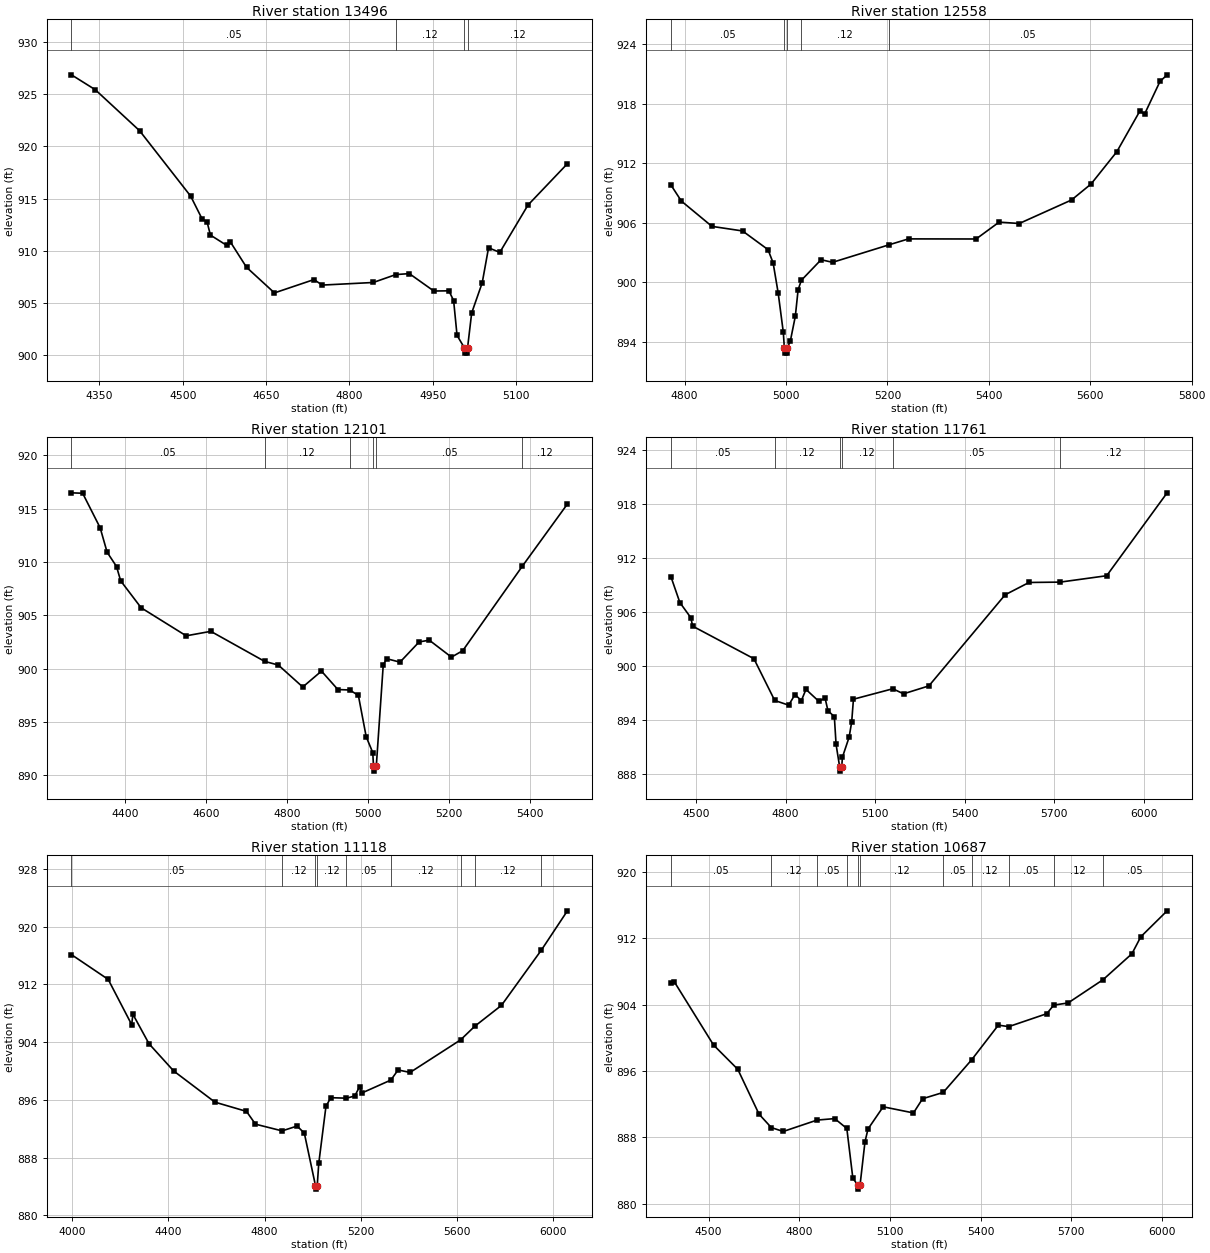
Type RM Length L Ch R = 1 ,13496   ,938,938,938
BEGIN DESCRIPTION:
MOSS CREEK 28.0
END DESCRIPTION:
XS GIS Cut Line= 3
      2880505.71     10190703.09       2881073.5       10190293.
      2881105.68     10190103.11
#Sta/Elev= 30
  4299.6  926.87  4342.5  925.44  4422.2  921.51  4514.2  915.23  4535.1  913.01
  4543.7  912.77  4549.8  911.49  4579.2   910.5  4585.4  910.86  4614.8   908.4
  4665.1  905.94  4736.3  907.22    4751  906.69    4843  906.94  4883.7   907.7
    4908  907.79  4952.1  906.12  4979.2  906.14  4987.7  905.21  4993.9  901.86
  5007.2  900.66  5007.7  900.16  5012.4  900.16  5012.8  900.66  5020.2  904.01
  5039.2  906.91  5050.6  910.27  5070.9  909.83  5121.6  914.37  5192.6  918.34
#Mann= 4 ,-1 , 0
  4299.6     .05       0  4883.7     .12       0  5007.2     .07       0
  5012.8     .12       0
Bank Sta=5007.2,5012.8
XS Rating Curve= 0 ,0
Exp/Cntr=0.3,0.1

Type RM Length L Ch R = 1 ,12558   ,457,457,457
BEGIN DESCRIPTION:
MOSS CREEK 27.0
END DESCRIPTION:
XS GIS Cut Line= 3
      2880905.68     10191053.11        2881131.       10191031.
      2881455.67     10190353.14
#Sta/Elev= 30
  4773.6  909.75  4793.7  908.17    4854  905.62  4914.3  905.16  4964.5  903.28
  4974.6  901.95  4984.6  898.91  4994.7  894.96  4996.8  893.35  4997.3  892.85
  5002.1  892.85  5002.5  893.35  5008.7   894.1  5018.4  896.56  5023.9  899.23
  5030.3  900.19  5069.2  902.26  5091.9     902  5203.6  903.77  5241.6  904.36
  5374.9  904.35  5420.3  906.05    5460  905.91  5563.1  908.28  5601.6  909.89
  5652.4  913.14  5697.7  917.23  5707.3  916.95  5737.5  920.22  5751.6  920.89
#Mann= 5 ,-1 , 0
  4773.6     .05       0  4996.8     .05       0  5002.5     .05       0
  5030.3     .12       0  5203.6     .05       0
Bank Sta=4996.8,5002.5
XS Rating Curve= 0 ,0
Exp/Cntr=0.3,0.1

Type RM Length L Ch R = 1 ,12101   ,340,340,340
BEGIN DESCRIPTION:
MOSS CREEK 26.0
END DESCRIPTION:
XS GIS Cut Line= 3
       2880755.7     10191153.11        2881479.       10191275.
      2881955.68     10191403.11
#Sta/Elev= 30
  4266.5  916.48  4294.2  916.44  4337.5   913.2  4354.7  910.91    4378  909.57
  4388.2  908.23  4438.9   905.7  4550.4  903.07  4611.3  903.49  4744.6  900.67
  4778.3  900.33  4838.8  898.27  4885.1  899.76  4925.7  898.03    4955  897.99
  4976.4  897.48  4995.8   893.6    5012  892.12  5013.8  890.88  5014.3  890.38
  5020.8  890.88    5038  900.37  5046.8  900.92  5079.4   900.6  5126.8   902.5
  5151.9  902.66  5206.7  901.07  5234.7  901.68  5382.1   909.6  5493.6  915.43
#Mann= 6 ,-1 , 0
  4266.5     .05       0  4744.6     .12       0    4955     .05       0
  5013.8     .03       0  5020.8     .05       0  5382.1     .12       0
Bank Sta=5013.8,5020.8
XS Rating Curve= 0 ,0
Exp/Cntr=0.3,0.1

Type RM Length L Ch R = 1 ,11761   ,643,643,643
BEGIN DESCRIPTION:
MOSS CREEK 25.0
END DESCRIPTION:
XS GIS Cut Line= 3
      2880805.64     10191253.09      2881448.28     10191642.55
      2882358.02     10191687.69
#Sta/Elev= 30
  4416.3  909.85  4445.4  907.06  4482.3  905.37  4488.1  904.44  4693.6  900.82
  4763.3  896.18    4810  895.66  4831.3  896.83  4852.7  896.17  4868.1  897.41
  4910.8   896.1  4932.2  896.43  4941.8  895.04  4963.2  894.38    4969  891.29
  4980.9  888.83  4981.4  888.33    4988  888.83  4990.3  889.88  5012.7   892.1
  5021.3  893.79  5027.2  896.32    5159  897.48  5195.2  896.92  5280.1   897.8
  5535.6  907.92  5615.7  909.29  5720.1  909.33    5876  910.04  6078.6  919.25
#Mann= 6 ,-1 , 0
  4416.3     .05       0  4763.3     .12       0  4980.9     .07       0
    4988     .12       0    5159     .05       0  5720.1     .12       0
Bank Sta=4980.9,4988
XS Rating Curve= 0 ,0
Exp/Cntr=0.3,0.1

Type RM Length L Ch R = 1 ,11118   ,431,431,431
BEGIN DESCRIPTION:
MOSS CREEK 24.0
END DESCRIPTION:
XS GIS Cut Line= 3
      2880434.43     10191923.81      2881219.11     10192031.44
      2882489.94     10192041.86
#Sta/Elev= 30
    3997  916.12  4149.7  912.69  4247.5  906.42  4252.5  907.86  4319.6  903.77
  4422.2     900  4593.8  895.68    4725   894.4  4762.4  892.63  4873.1   891.7
  4935.6  892.37  4965.6  891.39  5011.9  884.13  5012.4  883.63  5019.3  884.13
  5025.6  887.19  5055.6   895.1  5075.6   896.3  5140.9  896.23  5175.6  896.54
  5195.6  897.83  5205.6  896.96  5325.5  898.74  5355.6  900.14  5405.6   899.8
  5615.6  904.31  5674.7   906.2  5785.6  909.09  5951.8  916.76  6059.9  922.19
#Mann= 9 ,-1 , 0
    3997     .05       0  4873.1     .12       0  5011.9     .07       0
  5019.3     .12       0  5140.9     .05       0  5325.5     .12       0
  5615.6     .05       0  5674.7     .12       0  5951.8     .05       0
Bank Sta=5011.9,5019.3
XS Rating Curve= 0 ,0
Exp/Cntr=0.3,0.1

Type RM Length L Ch R = 1 ,10687   ,370,370,370
BEGIN DESCRIPTION:
MOSS CREEK 23.0
END DESCRIPTION:
XS GIS Cut Line= 3
      2880705.65     10192403.11      2881444.81     10192448.11
      2882342.41     10192517.42
#Sta/Elev= 30
  4376.4  906.65  4386.5  906.75  4516.7  899.12  4596.8   896.2    4667  890.81
  4707.6  889.19  4747.1  888.72  4858.9  890.09  4917.4  890.27  4957.5  889.08
  4977.5  883.08  4993.8  882.28  4994.3  881.78  5001.3  882.28  5017.6  887.48
  5027.6  889.02  5077.7  891.69    5178  890.95  5208.1  892.66  5276.4  893.42
  5370.3  897.34  5458.8  901.52  5493.1  901.34  5619.3   902.9  5641.8  903.93
  5689.5  904.19  5805.2  906.99  5900.7  910.11  5930.2  912.16  6017.2  915.28
#Mann= 11 ,-1 , 0
  4376.4     .05       0  4707.6     .12       0  4858.9     .05       0
  4957.5     .12       0  4993.8     .07       0  5001.3     .12       0
  5276.4     .05       0  5370.3     .12       0  5493.1     .05       0
  5641.8     .12       0  5805.2     .05       0
Bank Sta=4993.8,5001.3
XS Rating Curve= 0 ,0
Exp/Cntr=0.3,0.1

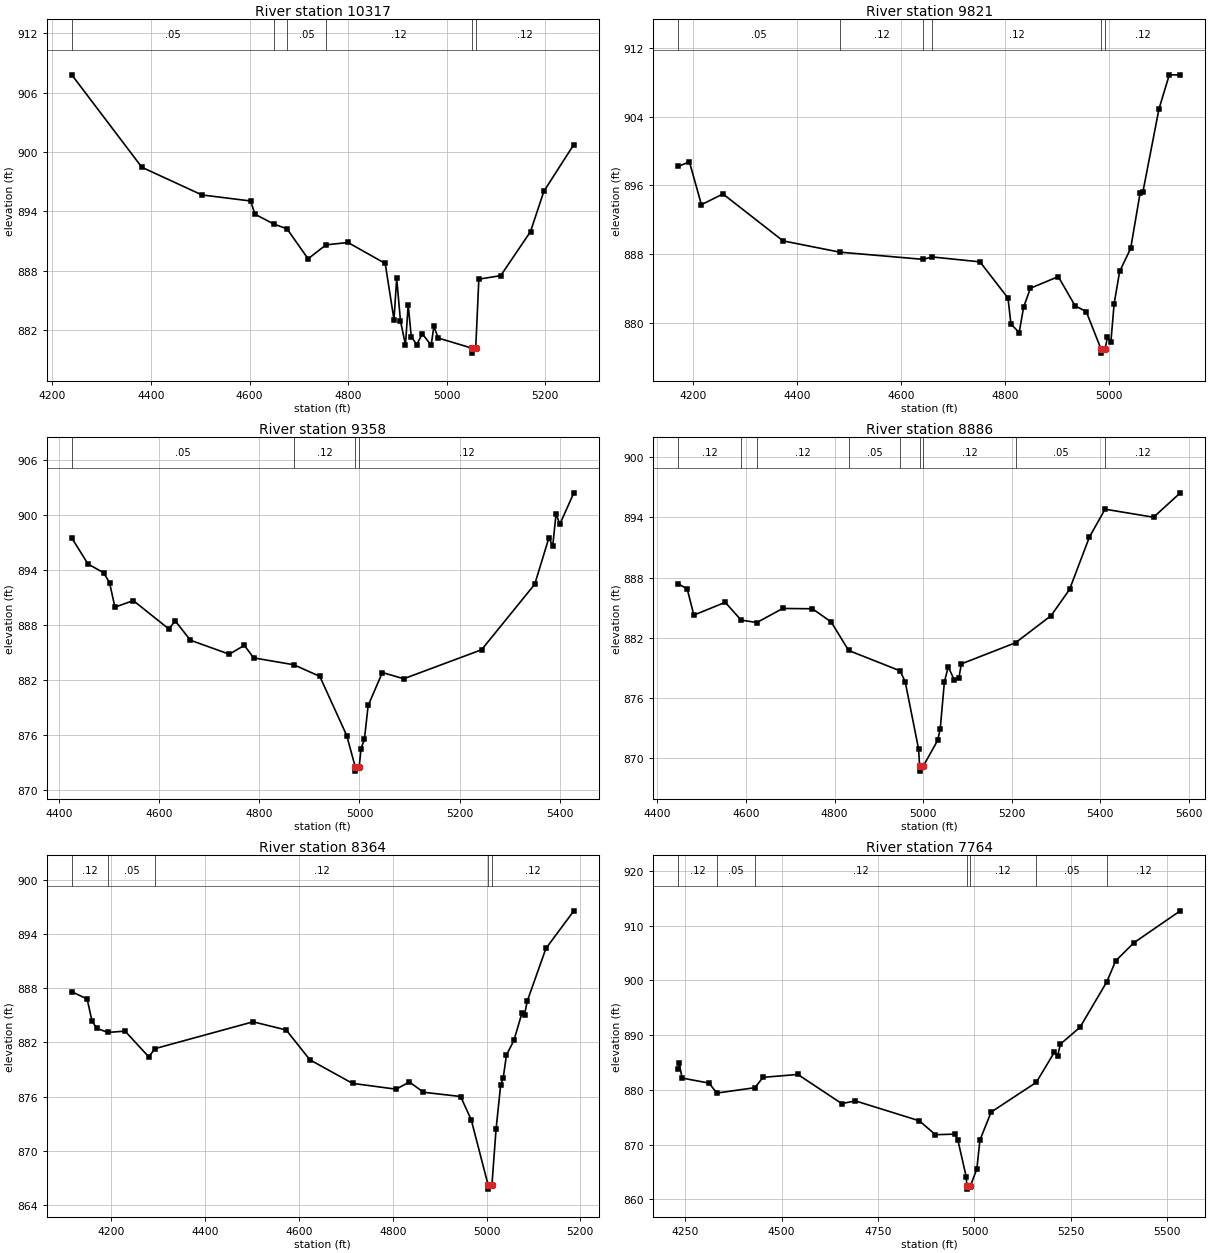
Type RM Length L Ch R = 1 ,10317   ,496,496,496
BEGIN DESCRIPTION:
MOSS CREEK 22.0
END DESCRIPTION:
XS GIS Cut Line= 3
      2880705.67     10192453.11       2881401.5       10192760.
      2881655.67     10192803.11
#Sta/Elev= 30
  4239.5  907.81  4381.6  898.46  4503.5  895.66  4602.2  895.05  4611.1  893.71
  4649.2  892.72  4676.1  892.23  4718.8   889.2  4755.1  890.61  4799.7  890.85
  4875.2  888.73    4893  883.05  4898.5  887.21  4906.2  882.91  4916.3   880.5
  4921.8  884.53  4928.1  881.33    4939  880.53  4950.6  881.61  4968.4  880.45
  4973.9  882.37  4982.7  881.19  5051.2  880.16  5051.7  879.66  5058.8  880.16
  5065.1  887.14  5109.5   887.5  5169.9  891.95    5197  896.03  5257.8  900.76
#Mann= 6 ,-1 , 0
  4239.5     .05       0  4649.2     .12       0  4676.1     .05       0
  4755.1     .12       0  5051.2     .07       0  5058.8     .12       0
Bank Sta=5051.2,5058.8
XS Rating Curve= 0 ,0
Exp/Cntr=0.3,0.1

Type RM Length L Ch R = 1 ,9821    ,463,463,463
BEGIN DESCRIPTION:
MOSS CREEK 21.0
END DESCRIPTION:
XS GIS Cut Line= 3
      2880805.69     10193503.11      2881576.25       10193199.
      2881705.66     10193153.12
#Sta/Elev= 30
  4171.6  898.21  4193.1  898.73  4216.2  893.75  4257.6     895  4373.2  889.54
  4482.2  888.23  4642.5  887.39  4659.9  887.67    4752   887.1  4805.9  882.88
  4811.5  879.86  4827.4  878.88  4835.9  881.82  4848.9  884.03  4902.6  885.38
  4934.9  881.99  4956.4  881.31  4984.6  876.98  4985.1  876.48  4992.7  876.98
    4997   878.3  5003.7  877.74    5010  882.22  5020.6  885.98  5041.8  888.66
  5060.1  895.15  5065.4  895.25  5096.3   904.9  5116.1  908.86  5137.3  908.85
#Mann= 6 ,-1 , 0
  4171.6     .05       0  4482.2     .12       0  4642.5     .05       0
  4659.9     .12       0  4984.6     .07       0  4992.7     .12       0
Bank Sta=4984.6,4992.7
XS Rating Curve= 0 ,0
Exp/Cntr=0.3,0.1

Type RM Length L Ch R = 1 ,9358    ,472,472,472
BEGIN DESCRIPTION:
MOSS CREEK 20.0
END DESCRIPTION:
XS GIS Cut Line= 3
      2880955.67     10193853.12      2881489.25       10193641.
      2881805.69     10193353.11
#Sta/Elev= 30
  4425.8  897.48  4458.1  894.64  4489.3  893.68  4501.1  892.61  4511.9  889.92
  4548.6  890.64  4619.5  887.54  4632.3  888.42  4662.6  886.31  4740.2  884.78
  4770.2  885.75  4788.8  884.38  4868.9  883.63  4920.8  882.36  4974.6  875.89
  4991.3  872.51  4991.8  872.01  4999.5  872.51  5003.1  874.47  5009.9  875.52
  5017.3  879.18  5045.7  882.78  5088.3   882.1  5243.7  885.27  5349.8  892.43
  5378.1  897.51  5385.6  896.56  5392.3  900.12  5399.8  898.97  5427.8  902.41
#Mann= 4 ,-1 , 0
  4425.8     .05       0  4868.9     .12       0  4991.3     .07       0
  4999.5     .12       0
Bank Sta=4991.3,4999.5
XS Rating Curve= 0 ,0
Exp/Cntr=0.3,0.1

Type RM Length L Ch R = 1 ,8886    ,522,522,522
BEGIN DESCRIPTION:
MOSS CREEK 19.0
END DESCRIPTION:
XS GIS Cut Line= 3
      2881285.77     10194310.17      2881802.45      10193986.3
      2881948.29     10193482.79
#Sta/Elev= 30
  4446.9  887.38  4467.1  886.88  4482.2  884.27    4553  885.54    4589  883.77
  4624.5  883.53  4682.8  884.93  4749.9   884.9  4792.3  883.59  4831.7  880.75
  4948.2  878.72  4959.7   877.6  4989.7  870.95  4992.1  869.24  4992.6  868.74
  5000.3  869.24  5032.7  871.79  5038.6  872.92    5048  877.61  5056.7  879.12
  5070.4  877.82  5080.8     878  5086.2  879.41  5208.8  881.52  5289.1  884.22
  5330.7  886.82  5375.7  892.05    5411  894.81  5520.5  894.01  5580.9  896.44
#Mann= 9 ,-1 , 0
  4446.9     .12       0    4589     .05       0  4624.5     .12       0
  4831.7     .05       0  4948.2     .12       0  4992.1     .07       0
  5000.3     .12       0  5208.8     .05       0    5411     .12       0
Bank Sta=4992.1,5000.3
XS Rating Curve= 0 ,0
Exp/Cntr=0.3,0.1

Type RM Length L Ch R = 1 ,8364    ,600,600,600
BEGIN DESCRIPTION:
MOSS CREEK 18.0
END DESCRIPTION:
XS GIS Cut Line= 3
      2881323.23     10194399.23      2882069.81     10194288.39
      2882355.65     10194153.13
#Sta/Elev= 30
  4115.3   887.6  4148.1   886.8  4158.2  884.42  4168.3  883.56  4192.5  883.11
    4229  883.25  4279.5  880.41  4292.9  881.32    4502  884.28  4572.7  883.38
  4623.3  880.08  4714.3  877.48  4807.1  876.84  4835.6  877.63  4865.5   876.5
  4944.7  876.03  4967.4  873.46  5003.2   866.3  5003.7   865.8  5011.6   866.3
  5020.4  872.44  5030.1  877.25  5035.7  878.12  5042.5  880.61  5058.4  882.22
  5075.6  885.25  5081.2  885.06  5086.8  886.55  5126.7  892.38  5186.3  896.54
#Mann= 5 ,-1 , 0
  4115.3     .12       0  4192.5     .05       0  4292.9     .12       0
  5003.2     .07       0  5011.6     .12       0
Bank Sta=5003.2,5011.6
XS Rating Curve= 0 ,0
Exp/Cntr=0.3,0.1

Type RM Length L Ch R = 1 ,7764    ,269,269,269
BEGIN DESCRIPTION:
MOSS CREEK 17.0
END DESCRIPTION:
XS GIS Cut Line= 4
      2881395.75      10194448.1      2881797.22     10194460.76
      2882135.78     10194930.75      2882451.23     10194989.68
#Sta/Elev= 30
  4231.9  883.79  4234.5  884.87  4241.8  882.16  4311.9  881.24  4331.8  879.42
  4430.4   880.4  4451.9  882.29    4542  882.82  4655.8   877.5  4691.4  877.99
    4857  874.36  4898.8  871.82  4949.1  871.93  4956.9  870.85  4978.5  864.16
  4980.3  862.39  4980.8  861.89    4989  862.39  5006.2  865.59  5014.1  870.83
  5043.2  875.95  5160.2  881.37  5206.8  886.83  5215.3  886.13  5222.9  888.36
  5273.7  891.44  5343.1  899.72  5366.1  903.55  5413.7  906.87  5533.7  912.68
#Mann= 7 ,-1 , 0
  4231.9     .12       0  4331.8     .05       0  4430.4     .12       0
  4980.3     .07       0    4989     .12       0  5160.2     .05       0
  5343.1     .12       0
Bank Sta=4980.3,4989
XS Rating Curve= 0 ,0
Exp/Cntr=0.3,0.1