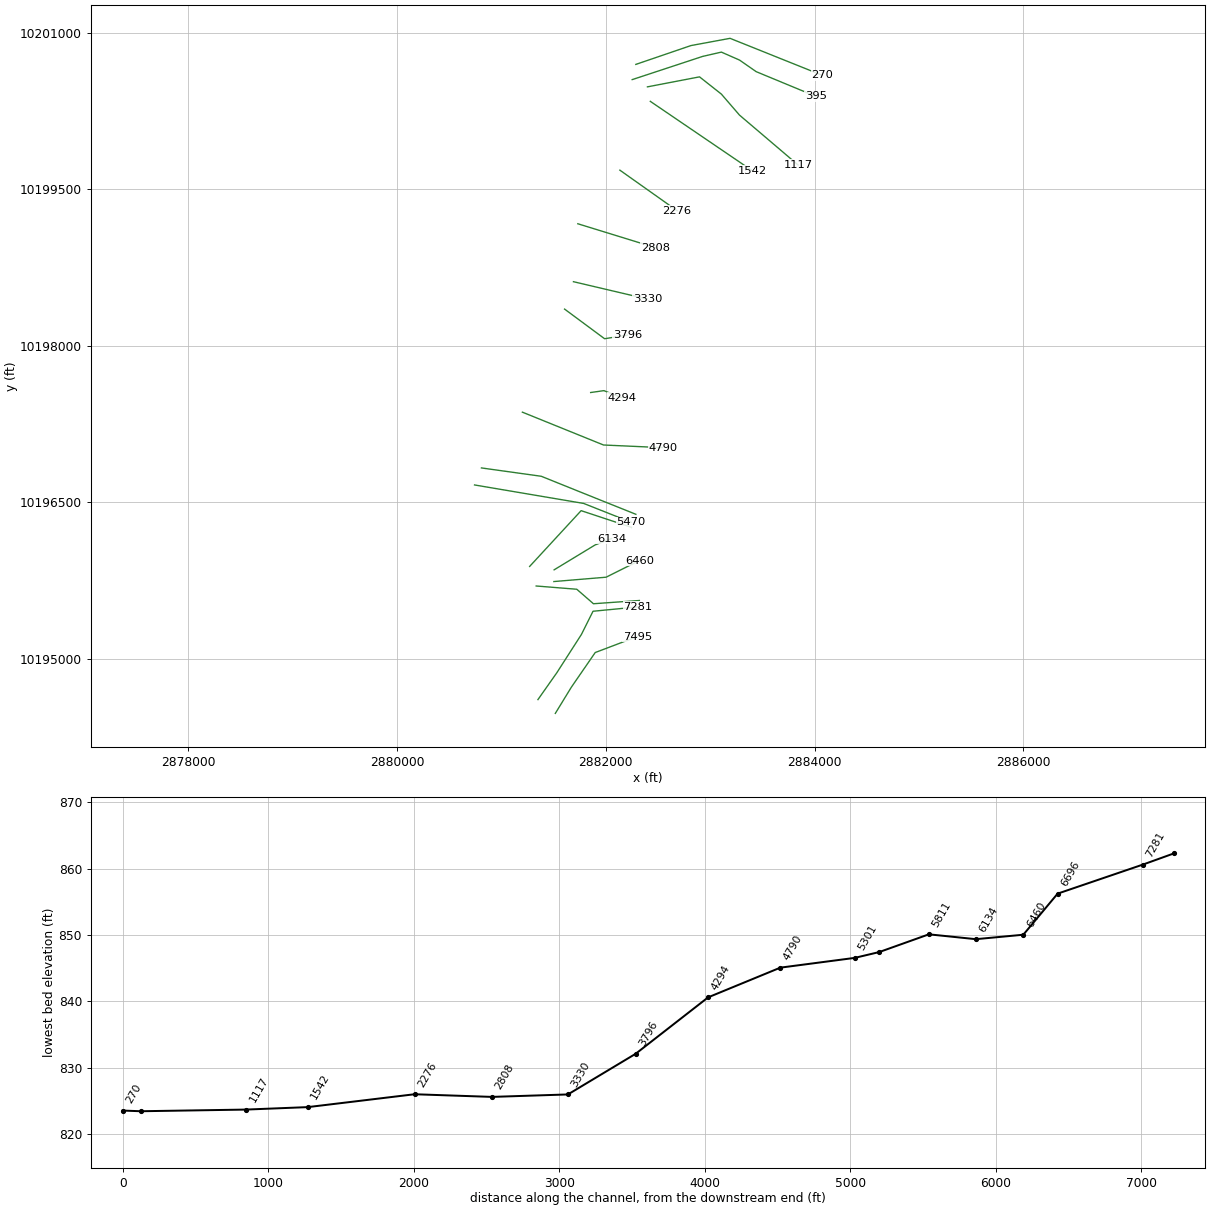
HEC-RAS study MOSS CREEK.prj: MOSS CREEK Base Level Engineering

--- MOSS CREEK.g01 (geometry) --- (continued)

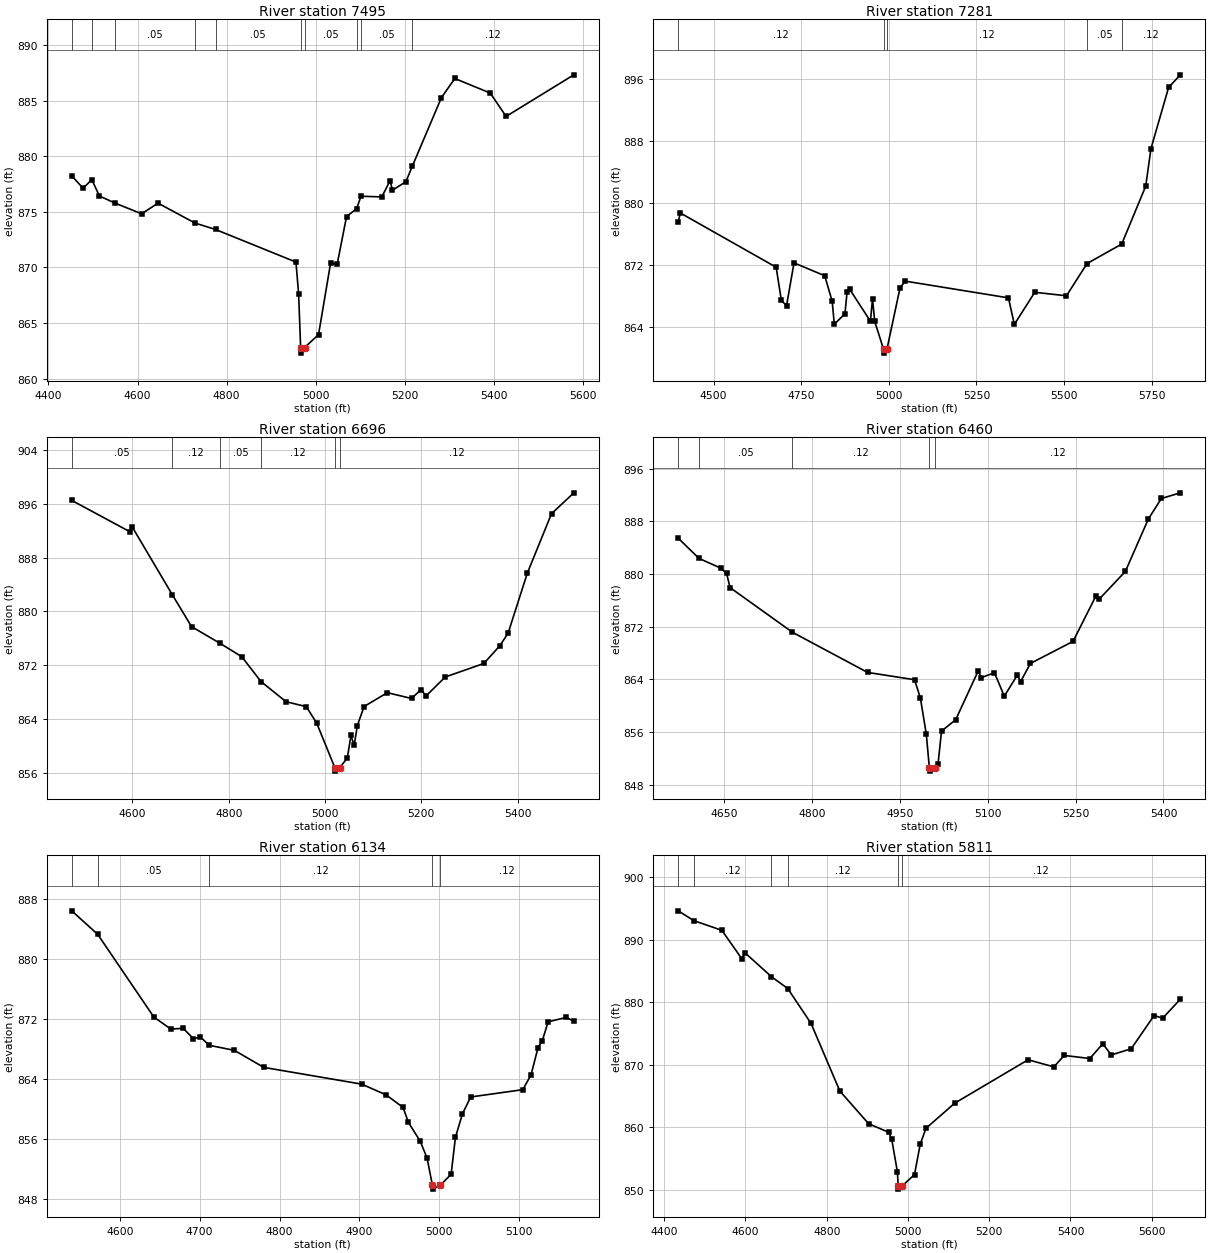
Type RM Length L Ch R = 1 ,7495    ,214,214,214
BEGIN DESCRIPTION:
Mapping XS cd000ddc
END DESCRIPTION:
XS GIS Cut Line= 4
      2881517.24     10194476.76      2881670.04     10194726.79
       2881899.2     10195060.13      2882301.31     10195212.65
#Sta/Elev= 30
  4452.3  878.23  4477.7  877.12  4497.3  877.89  4514.5  876.42  4549.6  875.78
  4609.3  874.82    4646  875.78  4728.9  873.99  4775.2  873.41  4955.8  870.48
  4961.8   867.6  4966.3  862.79  4966.8  862.29    4975  862.79  5006.5  863.95
  5033.5  870.37  5048.4  870.29  5069.4  874.57    5092  875.28  5101.9   876.4
  5148.6  876.34  5167.2   877.8  5172.6  876.94  5202.7  877.71  5217.1   879.1
  5282.5  885.27  5312.6  886.99  5392.1  885.68  5427.8  883.58  5579.9  887.32
#Mann= 10 ,-1 , 0
  4452.3     .05       0  4497.3     .12       0  4549.6     .05       0
  4728.9     .12       0  4775.2     .05       0  4966.3     .05       0
    4975     .05       0    5092     .12       0  5101.9     .05       0
  5217.1     .12       0
Bank Sta=4966.3,4975
XS Rating Curve= 0 ,0
Exp/Cntr=0.3,0.1

Type RM Length L Ch R = 1 ,7281    ,585,585,585
BEGIN DESCRIPTION:
Mapping XS 04219516
END DESCRIPTION:
XS GIS Cut Line= 5
      2881350.58     10194608.73      2881531.15     10194865.68
      2881767.26     10195233.74      2881878.37     10195455.96
      2882308.97     10195497.63
#Sta/Elev= 30
  4399.1  877.55  4404.9  878.71  4678.5   871.7  4693.3  867.41  4708.1  866.73
  4729.4  872.26    4817   870.6  4838.4  867.28  4844.3  864.33  4874.7  865.68
  4880.7  868.46  4888.3  868.85  4947.4  864.72  4953.4  867.62  4959.6   864.7
  4984.9   861.1  4985.4   860.6  4994.5   861.1    5032  869.06  5047.2   869.9
  5341.2  867.74    5358  864.31  5416.2  868.46  5506.7  868.01  5565.5  872.18
  5664.3  874.69  5732.7  882.16  5747.8  887.03  5798.1  894.93  5831.5  896.56
#Mann= 5 ,-1 , 0
  4399.1     .12       0  4984.9     .07       0  4994.5     .12       0
  5565.5     .05       0  5664.3     .12       0
Bank Sta=4984.9,4994.5
XS Rating Curve= 0 ,0
Exp/Cntr=0.3,0.1

Type RM Length L Ch R = 1 ,6696    ,236,236,236
BEGIN DESCRIPTION:
Mapping XS 148be102
END DESCRIPTION:
XS GIS Cut Line= 4
      2881333.68     10195698.11      2881722.59     10195666.86
      2881882.31     10195527.97      2882321.98     10195559.13
#Sta/Elev= 30
  4474.1  896.54  4595.2  891.86  4600.2  892.52  4682.6  882.53  4722.8  877.75
    4782  875.26  4827.2  873.26    4867  869.57    4919  866.57  4961.1  865.83
  4982.6   863.4  5020.5  856.73    5021  856.23  5030.2  856.73  5046.2  858.16
  5053.9  861.55  5060.5  860.05  5067.1  863.01  5081.1  865.85  5129.4  867.91
  5179.6  867.05  5199.6  868.38  5209.6  867.41  5249.7  870.25  5329.9  872.26
  5362.9  874.89  5380.1  876.76  5420.2  885.73  5470.3  894.56  5516.7  897.67
#Mann= 6 ,-1 , 0
  4474.1     .05       0  4682.6     .12       0    4782     .05       0
    4867     .12       0  5020.5     .07       0  5030.2     .12       0
Bank Sta=5020.5,5030.2
XS Rating Curve= 0 ,0
Exp/Cntr=0.3,0.1

Type RM Length L Ch R = 1 ,6460    ,326,326,326
BEGIN DESCRIPTION:
Mapping XS 1b271955
END DESCRIPTION:
XS GIS Cut Line= 3
      2881503.37     10195740.68      2882003.37     10195782.35
      2882321.75     10195941.54
#Sta/Elev= 30
  4571.1  885.43  4606.7  882.36  4643.7  880.89  4653.7  880.09  4659.6  877.93
  4766.2  871.14  4894.5  865.04  4974.8  863.93  4984.8  861.13  4994.9  855.64
  5000.1  850.54  5000.6  850.04  5009.8  850.54  5014.9  851.12  5020.9  856.13
  5045.1  857.85  5083.4  865.24    5089  864.25  5111.3     865  5128.1  861.43
  5150.4  864.63    5156  863.65  5172.8  866.41  5245.5  869.75  5284.6  876.65
  5290.2  876.17  5334.9  880.38  5374.1  888.33  5396.4  891.47  5428.8  892.33
#Mann= 5 ,-1 , 0
  4571.1     .12       0  4606.7     .05       0  4766.2     .12       0
  5000.1     .07       0  5009.8     .12       0
Bank Sta=5000.1,5009.8
XS Rating Curve= 0 ,0
Exp/Cntr=0.3,0.1

Type RM Length L Ch R = 1 ,6134    ,323,323,323
BEGIN DESCRIPTION:
MOSS CREEK 13.0
END DESCRIPTION:
XS GIS Cut Line= 3
      2881505.65     10195853.09      2881898.75       10196092.
      2882055.67     10196153.11
#Sta/Elev= 30
    4540  886.45  4572.5  883.31  4642.7   872.3    4664  870.69  4679.5   870.8
  4692.2  869.41  4700.9  869.64  4712.2  868.53  4743.5  867.86  4780.3  865.59
  4902.8  863.36  4933.4  861.93  4954.7  860.25  4961.3  858.27  4976.1  855.75
  4984.7  853.51  4991.4  849.87  4991.9  849.37  5001.1  849.87  5014.8  851.35
  5020.2  856.27  5028.9  859.38  5039.3  861.65  5104.5  862.62  5114.8  864.59
  5123.6  868.23    5129  869.17  5136.2  871.66  5158.8  872.25  5168.4  871.75
#Mann= 5 ,-1 , 0
    4540     .12       0  4572.5     .05       0  4712.2     .12       0
  4991.4     .07       0  5001.1     .12       0
Bank Sta=4991.4,5001.1
XS Rating Curve= 0 ,0
Exp/Cntr=0.3,0.1

Type RM Length L Ch R = 1 ,5811    ,341,341,341
BEGIN DESCRIPTION:
Mapping XS 2e75c1fe
END DESCRIPTION:
XS GIS Cut Line= 3
      2881271.23     10195885.64      2881764.25     10196420.33
      2882246.91      10196260.6
#Sta/Elev= 30
  4434.6  894.63  4472.9  893.06  4541.9  891.51  4591.8   886.9  4598.6  887.93
  4664.1  884.09  4704.2  882.19  4761.4  876.62  4832.3   865.8  4903.1  860.57
  4952.5  859.19  4959.9  858.13    4974  852.87  4975.9   850.6  4976.4   850.1
  4985.7   850.6  5016.1  852.43  5030.2   857.3  5044.3  859.83  5115.2  863.86
  5295.7   870.8  5359.1  869.66  5384.6  871.49  5447.8     871  5479.4  873.36
  5500.5  871.57  5549.4  872.56  5605.8  877.88  5626.9  877.45  5670.3  880.48
#Mann= 6 ,-1 , 0
  4434.6     .05       0  4472.9     .12       0  4664.1     .05       0
  4704.2     .12       0  4975.9     .07       0  4985.7     .12       0
Bank Sta=4975.9,4985.7
XS Rating Curve= 0 ,0
Exp/Cntr=0.3,0.1

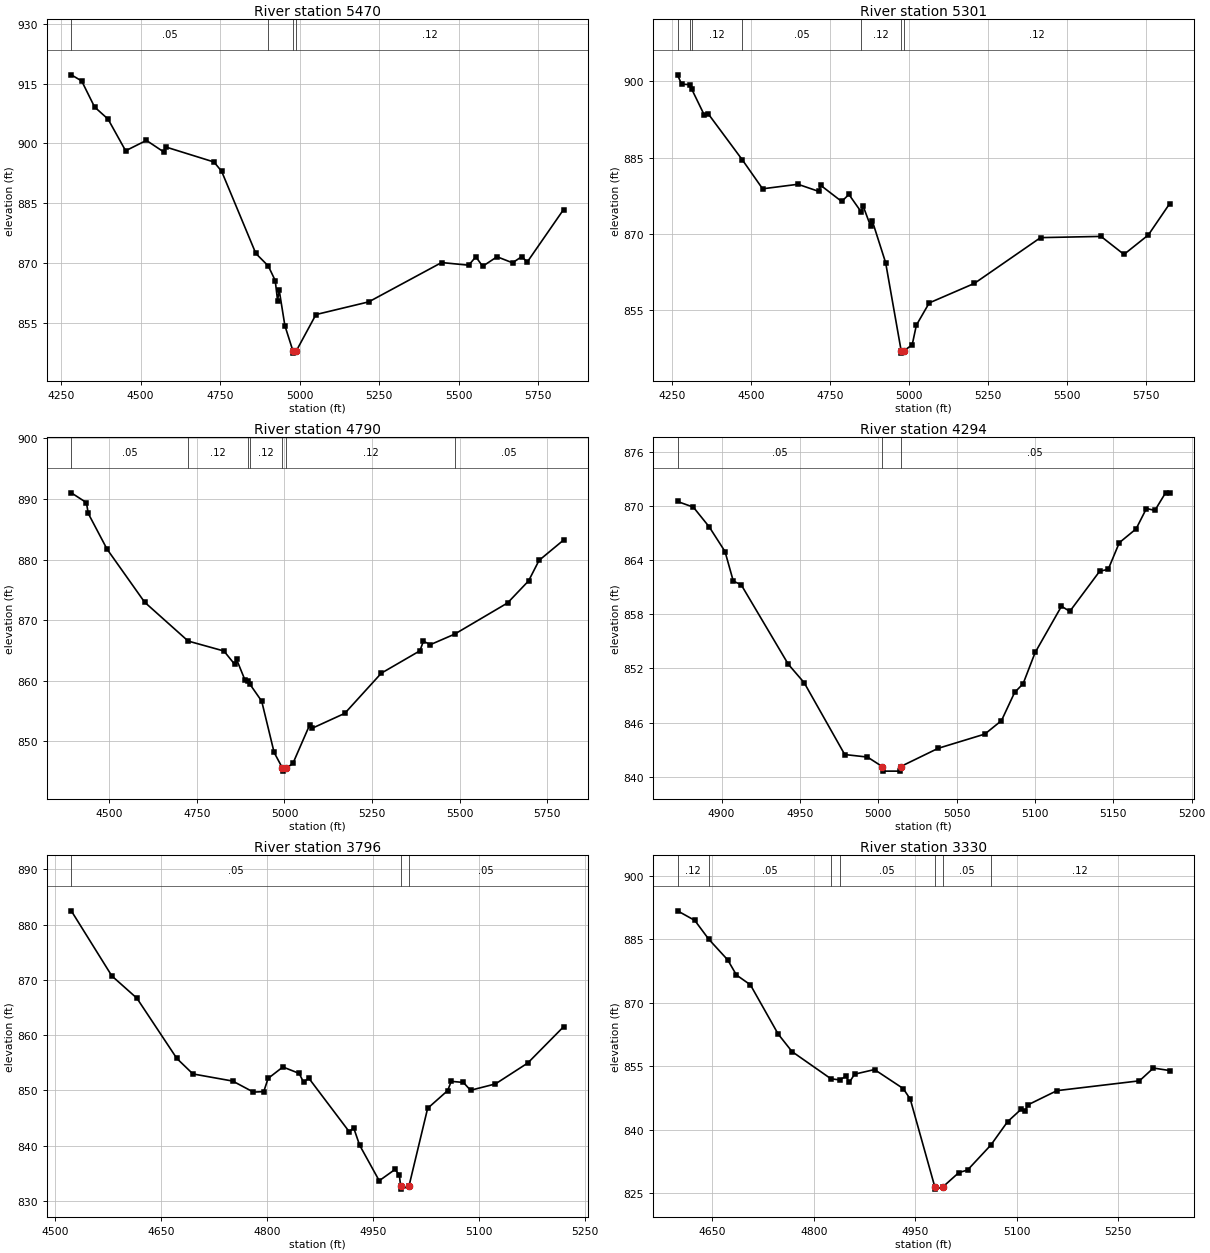
Type RM Length L Ch R = 1 ,5470    ,169,169,169
BEGIN DESCRIPTION:
Mapping XS 8ca00213
END DESCRIPTION:
XS GIS Cut Line= 3
       2880743.4     10196666.86      2881788.56     10196489.78
      2882242.08     10196309.75
#Sta/Elev= 30
    4282   917.2  4314.7  915.66  4355.3  909.13  4397.6   906.1  4452.9  898.16
  4518.3  900.76  4573.6  897.82  4578.7  899.12  4730.6  895.35  4754.7  893.03
  4862.4  872.41  4901.4  869.29  4923.3  865.63  4930.7  860.62  4935.8  863.23
  4953.7  854.32  4979.2  847.93  4979.7  847.43  4989.2  847.93  5051.4   857.1
  5217.4  860.28  5446.6  870.14  5531.8  869.47  5554.1  871.58  5575.7   869.2
  5620.8  871.59  5669.5  870.08  5699.2  871.65  5715.5  870.23    5830  883.42
#Mann= 4 ,-1 , 0
    4282     .05       0  4901.4     .12       0  4979.2     .07       0
  4989.2     .12       0
Bank Sta=4979.2,4989.2
XS Rating Curve= 0 ,0
Exp/Cntr=0.3,0.1

Type RM Length L Ch R = 1 ,5301    ,511,511,511
BEGIN DESCRIPTION:
MOSS CREEK 11.0
END DESCRIPTION:
XS GIS Cut Line= 4
      2880809.39     10196830.05      2881382.31     10196750.19
      2881812.86     10196576.58      2882288.56     10196385.61
#Sta/Elev= 30
  4268.5  901.27  4281.2  899.44    4307  899.34  4313.1  898.49  4352.8   893.4
  4365.7  893.59  4473.3  884.55  4537.4  878.86  4649.1  879.75  4715.6  878.33
  4720.7  879.55  4787.2  876.37    4810  877.75  4849.3  874.27  4854.3  875.57
  4878.4  871.55  4883.8  872.57  4926.1  864.32    4975  847.05  4975.5  846.55
    4985  847.05    5010   848.2  5023.1  852.04  5063.7  856.42  5206.4  860.26
  5415.5  869.26  5606.5   869.5  5679.1  865.96    5756  869.78  5823.8  875.97
#Mann= 7 ,-1 , 0
  4268.5     .12       0    4307     .05       0  4313.1     .12       0
  4473.3     .05       0  4849.3     .12       0    4975     .07       0
    4985     .12       0
Bank Sta=4975,4985
XS Rating Curve= 0 ,0
Exp/Cntr=0.3,0.1

Type RM Length L Ch R = 1 ,4790    ,496,496,496
BEGIN DESCRIPTION:
MOSS CREEK 10.0
END DESCRIPTION:
XS GIS Cut Line= 3
      2881201.79     10197364.76      2881978.87     10197049.94
      2882545.47      10197024.5
#Sta/Elev= 30
  4391.3  891.02  4434.4  889.41  4439.8  887.61  4493.5  881.72  4600.7  872.97
    4725  866.55  4827.1  864.91  4857.9  862.71  4863.3  863.52  4887.4   860.1
  4896.9  859.98  4901.2  859.44    4935  856.63  4970.5  848.16  4994.3  845.58
  4994.8  845.08  5005.8  845.58  5024.1  846.35  5072.3  852.75  5077.7  852.12
  5172.3  854.62  5276.6  861.25  5386.7  864.94  5396.7  866.52  5416.7  865.96
  5485.8  867.69    5637  872.84    5697  876.48    5727  879.87  5796.9  883.22
#Mann= 7 ,-1 , 0
  4391.3     .05       0    4725     .12       0  4896.9     .05       0
  4901.2     .12       0  4994.3     .07       0  5005.8     .12       0
  5485.8     .05       0
Bank Sta=4994.3,5005.8
XS Rating Curve= 0 ,0
Exp/Cntr=0.3,0.1

Type RM Length L Ch R = 1 ,4294    ,498,498,498
BEGIN DESCRIPTION:
MOSS CREEK 9.0
END DESCRIPTION:
XS GIS Cut Line= 3
      2881855.66     10197553.11       2881982.5       10197571.
      2882155.67     10197503.12
#Sta/Elev= 30
  4871.9  870.52    4882  869.89  4892.1  867.71  4902.2  864.97  4907.5  861.68
  4912.5  861.29  4942.6  852.46  4952.7  850.42  4978.6  842.45  4993.1  842.17
  5002.6  841.11  5003.1  840.61  5013.7  840.61  5014.2  841.11  5038.2  843.14
    5068  844.72  5078.6  846.21    5087  849.34  5092.4   850.3  5100.1  853.77
  5116.9   858.9  5122.2  858.33  5141.3  862.79  5146.7  862.99  5153.8  865.95
  5164.5  867.48  5171.1  869.74  5176.5  869.53  5183.3  871.48    5186  871.48
#Mann= 3 ,-1 , 0
  4871.9     .05       0  5002.6     .05       0  5014.2     .05       0
Bank Sta=5002.6,5014.2
XS Rating Curve= 0 ,0
Exp/Cntr=0.3,0.1

Type RM Length L Ch R = 1 ,3796    ,466,466,466
BEGIN DESCRIPTION:
MOSS CREEK 8.0
END DESCRIPTION:
XS GIS Cut Line= 3
      2881605.71      10198353.1      2881988.75       10198069.
      2882205.68     10198103.11
#Sta/Elev= 30
  4523.1  882.51  4580.5  870.72  4615.9  866.69  4672.5  855.77  4695.2  852.97
  4751.5  851.68  4780.8  849.68  4795.4  849.77  4801.6  852.16  4822.5  854.23
  4845.5  853.07  4851.7  851.48  4859.2   852.2  4916.4   842.5  4922.6  843.23
    4931  840.09  4958.8  833.63  4981.1  835.67  4987.3  834.67  4989.1  832.61
  4989.6  832.11  5000.8  832.61  5027.3  846.74  5055.6  849.95  5060.7  851.63
  5077.9  851.43    5088  850.01  5123.2  851.16    5169  854.95  5219.6  861.51
#Mann= 3 ,-1 , 0
  4523.1     .05       0  4989.1     .05       0  5000.8     .05       0
Bank Sta=4989.1,5000.8
XS Rating Curve= 0 ,0
Exp/Cntr=0.3,0.1

Type RM Length L Ch R = 1 ,3330    ,522,522,522
BEGIN DESCRIPTION:
Mapping XS e9deb862
END DESCRIPTION:
XS GIS Cut Line= 2
      2881690.86     10198615.69      2882399.21     10198449.01
#Sta/Elev= 30
  4598.6  891.71  4624.1  889.45  4644.8     885  4672.8  880.12  4685.7  876.55
  4706.3  874.24  4747.4   862.6  4767.9  858.46  4825.4  852.04  4838.3  851.78
  4847.5  852.62  4852.6  851.21  4860.4  853.13  4889.8  854.22  4932.2  849.74
  4942.6  847.26    4979  826.48  4979.5  825.98  4990.7  826.48  5014.5  829.89
  5027.3  830.48  5061.9  836.41  5086.4  841.89  5106.9  844.89    5112   844.5
  5117.2  845.93  5159.5  849.24  5281.5  851.56  5302.1  854.58  5326.3  853.98
#Mann= 7 ,-1 , 0
  4598.6     .12       0  4644.8     .05       0  4825.4     .12       0
  4838.3     .05       0    4979     .05       0  4990.7     .05       0
  5061.9     .12       0
Bank Sta=4979,4990.7
XS Rating Curve= 0 ,0
Exp/Cntr=0.3,0.1

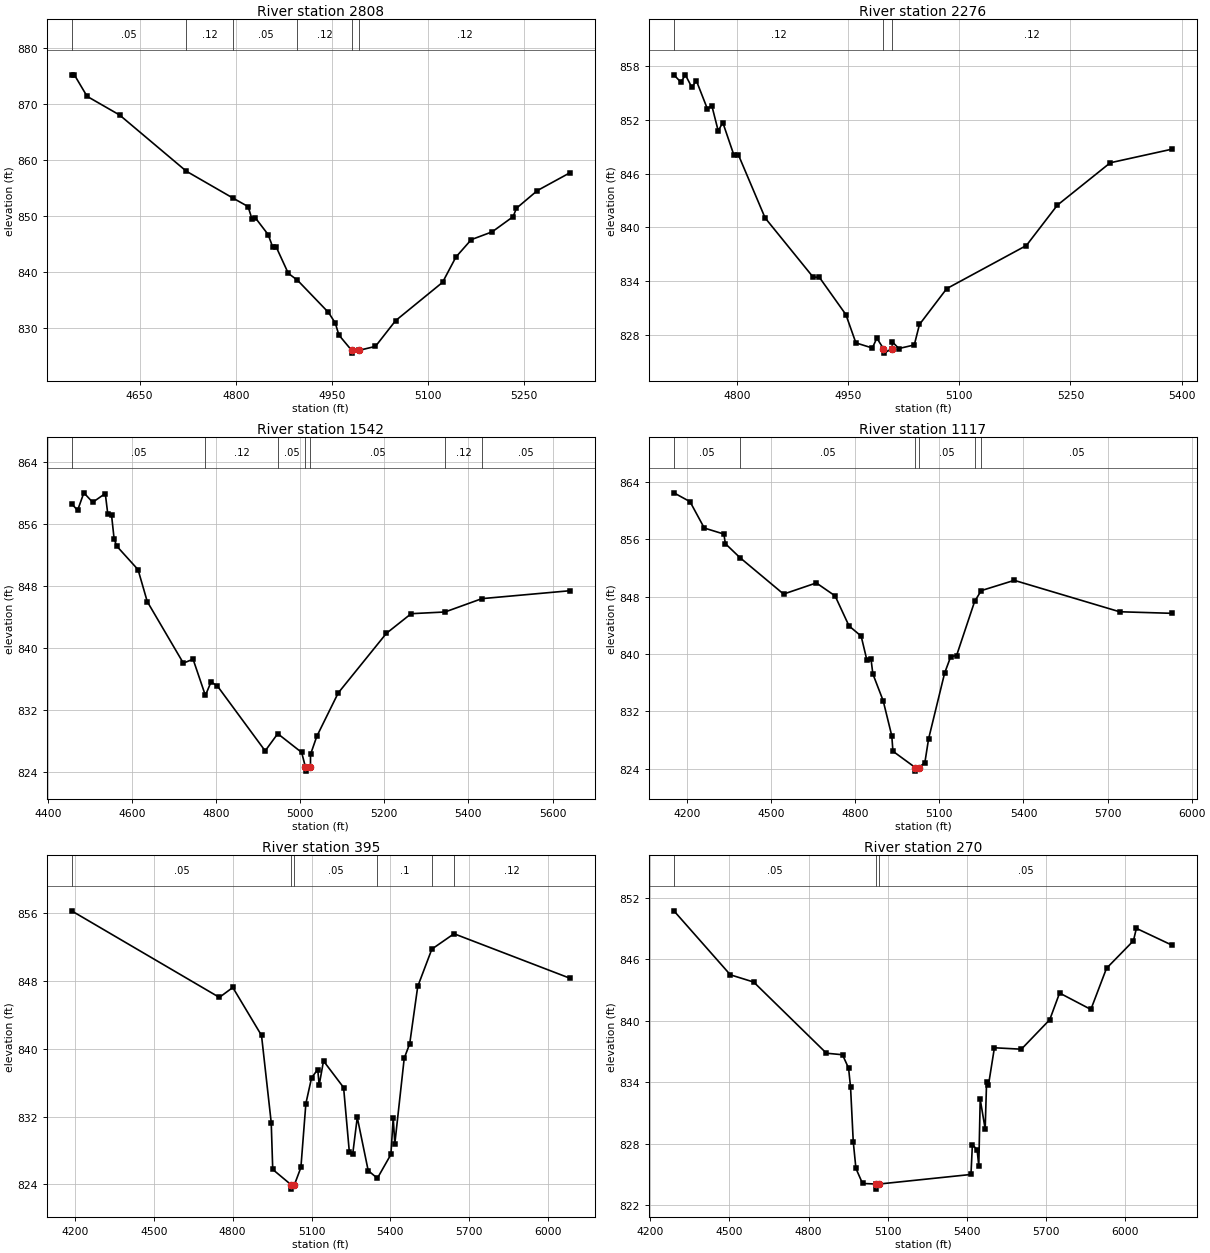
Type RM Length L Ch R = 1 ,2808    ,532,532,532
BEGIN DESCRIPTION:
Mapping XS 2f3174dc
END DESCRIPTION:
XS GIS Cut Line= 2
      2881732.54     10199171.24      2882475.61     10198942.07
#Sta/Elev= 30
  4543.9  875.15  4548.2  875.15  4568.1  871.32  4618.8     868  4722.9     858
  4796.2  853.18  4819.3   851.7  4825.2  849.56  4830.5  849.72  4850.7   846.7
  4857.9  844.45  4863.1  844.53  4882.1  839.81  4896.4  838.59  4944.8  832.85
  4955.3  830.98  4961.1  828.82  4980.9  826.11  4981.4  825.61  4992.6  826.11
  5018.1  826.81  5049.5  831.39  5122.8  838.21  5143.7  842.72  5167.6  845.81
  5200.2   847.2  5232.9   849.9  5238.1   851.4  5270.8  854.55  5321.5  857.71
#Mann= 6 ,-1 , 0
  4543.9     .05       0  4722.9     .12       0  4796.2     .05       0
  4896.4     .12       0  4980.9     .07       0  4992.6     .12       0
Bank Sta=4980.9,4992.6
XS Rating Curve= 0 ,0
Exp/Cntr=0.3,0.1

Type RM Length L Ch R = 1 ,2276    ,734,734,734
BEGIN DESCRIPTION:
Mapping XS 1242c77f
END DESCRIPTION:
XS GIS Cut Line= 2
      2882135.29     10199685.14      2882683.93     10199296.23
#Sta/Elev= 30
  4714.9  856.99  4724.3  856.17  4730.4  856.98  4739.1   855.6  4745.2  856.34
    4760  853.22  4766.1  853.55  4774.7  850.75  4780.9  851.68  4795.6  848.12
  4801.8  848.11    4838  841.06  4902.7  834.48  4911.3  834.44    4947   830.3
  4960.5  827.15  4982.7  826.58  4988.8  827.68  4997.7  826.51  4998.2  826.01
  5009.5  826.51  5009.7  827.27  5018.4  826.52  5039.3  826.92  5046.3   829.2
  5083.1  833.19  5190.6  837.99  5232.4  842.48  5303.8   847.2  5387.4  848.72
#Mann= 3 ,-1 , 0
  4714.9     .12       0  4997.7     .07       0  5009.5     .12       0
Bank Sta=4997.7,5009.5
XS Rating Curve= 0 ,0
Exp/Cntr=0.3,0.1

Type RM Length L Ch R = 1 ,1542    ,425,425,425
BEGIN DESCRIPTION:
Mapping XS 5329a3e8
END DESCRIPTION:
XS GIS Cut Line= 2
      2882426.95     10200344.87      2883406.14     10199678.19
#Sta/Elev= 30
  4456.6  858.58  4470.9  857.71  4485.8  859.97  4506.8  858.75  4536.7  859.88
  4542.7  857.22  4551.6   857.1  4557.7  854.04  4563.9   853.1  4614.6  850.06
  4636.5  845.94  4722.3     838  4745.4  838.51  4774.7  833.83  4788.1  835.57
    4803  835.07  4916.8  826.68  4946.7   828.9  5003.6  826.48  5012.6  824.57
  5013.1  824.07  5024.5  824.57  5024.6  826.22  5039.5  828.55  5090.4  834.15
  5205.1  841.85  5263.9  844.38  5344.4   844.6    5432  846.32  5641.2  847.34
#Mann= 7 ,-1 , 0
  4456.6     .05       0  4774.7     .12       0  4946.7     .05       0
  5012.6     .03       0  5024.5     .05       0  5344.4     .12       0
    5432     .05       0
Bank Sta=5012.6,5024.5
XS Rating Curve= 0 ,0
Exp/Cntr=0.3,0.1

Type RM Length L Ch R = 1 ,1117    ,722,722,722
BEGIN DESCRIPTION:
Mapping XS ac5c68d1
END DESCRIPTION:
XS GIS Cut Line= 5
      2882399.19     10200483.74      2882898.14     10200579.61
      2883107.54     10200414.29      2883281.15     10200212.91
      2883842.14     10199735.02
#Sta/Elev= 30
  4152.9  862.43  4210.4   861.2  4261.3  857.53  4331.3  856.69  4336.4  855.36
  4388.6  853.41  4544.2  848.34    4661  849.89  4727.9  848.09  4777.6  843.91
  4820.9  842.49  4841.7   839.1  4856.2  839.27  4862.6  837.24  4899.5  833.49
  4930.2  828.61  4934.3  826.47  5013.9   824.2  5014.4   823.7  5025.8   824.2
  5048.1  824.86  5061.5  828.19  5118.6  837.33  5140.5  839.64  5161.3  839.78
  5225.8  847.32  5249.3  848.82  5367.2  850.25  5742.8  845.88  5930.6  845.66
#Mann= 6 ,-1 , 0
  4152.9     .05       0  4388.6     .05       0  5013.9     .05       0
  5025.8     .05       0  5225.8     .12       0  5249.3     .05       0
Bank Sta=5013.9,5025.8
XS Rating Curve= 0 ,0
Exp/Cntr=0.3,0.1

Type RM Length L Ch R = 1 ,395     ,125,125,125
BEGIN DESCRIPTION:
Mapping XS ee04a120
END DESCRIPTION:
XS GIS Cut Line= 6
      2882253.36     10200553.18      2882926.98     10200775.41
      2883107.54     10200817.07      2883281.15     10200740.68
      2883440.87     10200629.57      2884010.29     10200393.47
#Sta/Elev= 30
  4187.3  856.24  4749.4  846.04  4800.5  847.21  4909.7  841.56  4946.6   831.3
  4952.4  825.77  5022.8  823.95  5023.3  823.45  5034.7  823.95  5059.5     826
  5078.4  833.53  5100.2  836.58  5123.6  837.54    5129   835.7  5145.5  838.55
  5221.9  835.42  5243.8   827.8  5256.7  827.61  5273.9   831.9  5315.5  825.63
  5350.4  824.73  5401.9  827.54  5410.6  831.87  5416.7  828.79  5452.5  838.87
  5473.4  840.59  5503.9  847.33  5557.6  851.73  5641.9  853.54  6082.6   848.3
#Mann= 6 ,-1 , 0
  4187.3     .05       0  5022.8     .03       0  5034.7     .05       0
  5350.4      .1       0  5557.6     .05       0  5641.9     .12       0
Bank Sta=5022.8,5034.7
XS Rating Curve= 0 ,0
Exp/Cntr=0.3,0.1

Type RM Length L Ch R = 1 ,270     ,0,0,0
BEGIN DESCRIPTION:
MOSS CREEK 1.0
END DESCRIPTION:
XS GIS Cut Line= 4
      2882288.09     10200699.02      2882815.87     10200879.57
      2883190.87     10200949.02      2884071.71     10200595.29
#Sta/Elev= 30
  4289.9   850.7  4503.7  844.46  4592.3  843.75  4867.9  836.81  4928.9  836.66
  4951.9  835.35  4959.4  833.47  4969.6  828.17  4979.7  825.57  5004.8   824.1
  5056.8  824.05  5057.3  823.55  5068.7  824.05  5415.7  824.98  5421.1   827.9
    5439  827.38  5445.3  825.81  5450.7  832.32  5469.5  829.41  5474.9  834.03
  5482.1  833.72  5504.5  837.34  5606.6   837.2  5714.2  840.08  5751.5  842.68
  5870.1  841.08  5929.3  845.09  6031.4  847.78  6042.5  848.99  6178.3  847.34
#Mann= 3 ,-1 , 0
  4289.9     .05       0  5056.8     .03       0  5068.7     .05       0
Bank Sta=5056.8,5068.7
XS Rating Curve= 0 ,0
Exp/Cntr=0.3,0.1

Chan Stop Cuts=-1
Use User Specified Reach Order=0
Composite Channel Slope=5