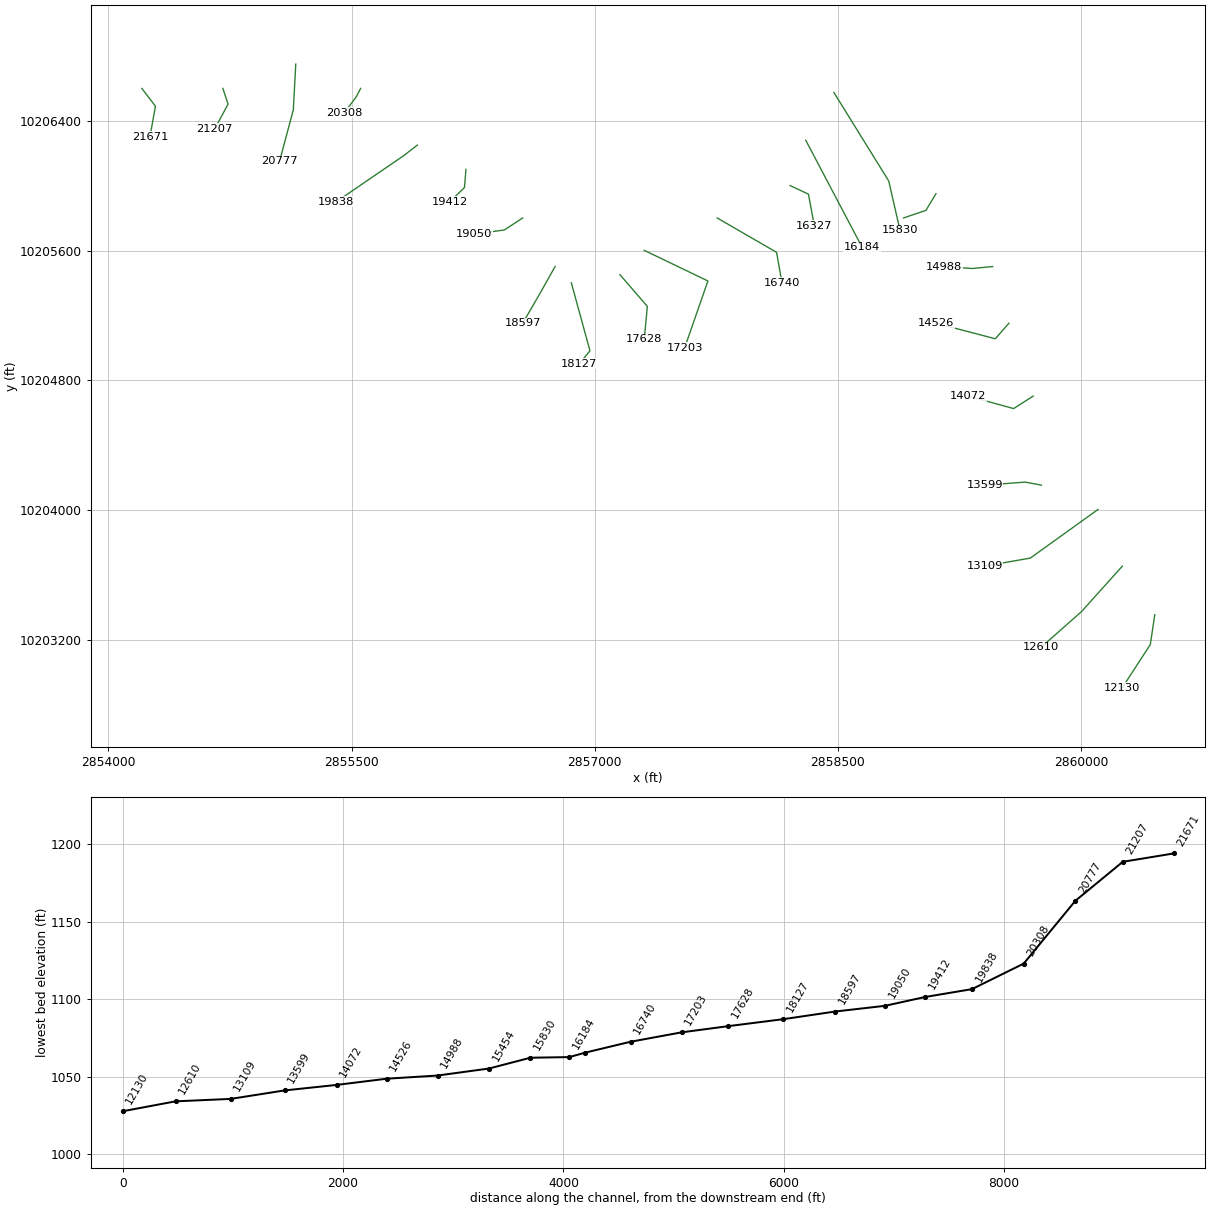
HEC-RAS study BEDFORD CREEK.prj: BEDFORD CREEK Base Level Engineering

--- BEDFORD CREEK.g01 (geometry) --- (continued)

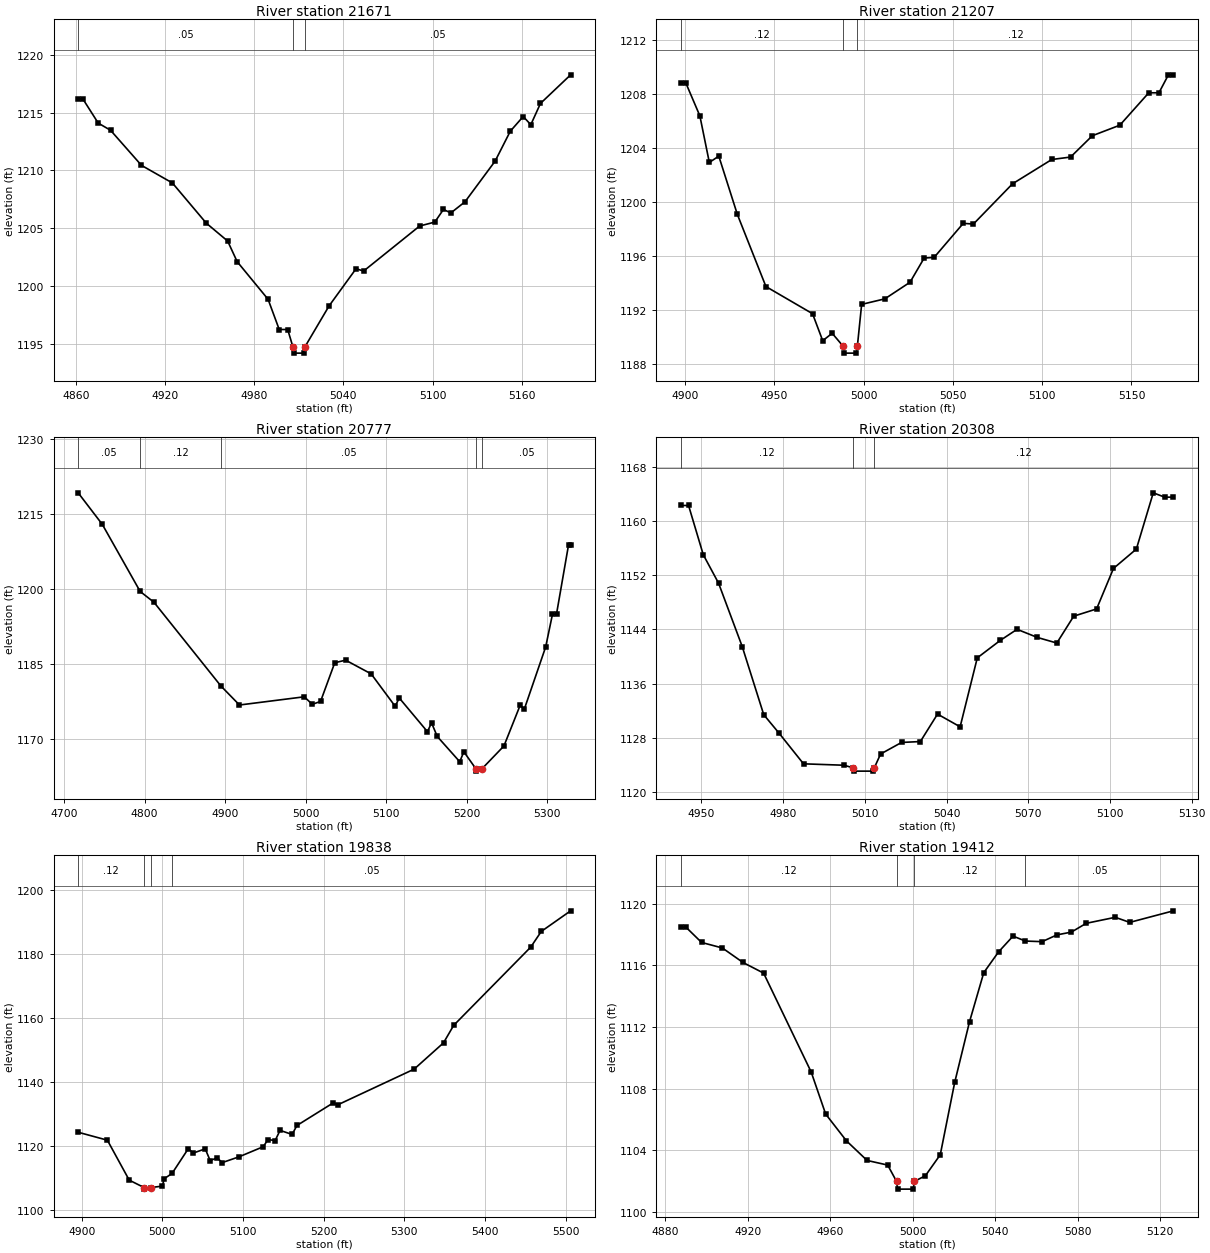
Type RM Length L Ch R = 1,21671,464,464,464
BEGIN DESCRIPTION:
BEDFORD CREEK 46.0
END DESCRIPTION:
XS GIS Cut Line= 3
      2854205.70     10206603.08      2854289.75     10206493.00
      2854255.69     10206303.13
#Sta/Elev= 30
  4861.5 1216.19  4864.6 1216.19  4875.0 1214.09  4883.3 1213.47  4904.1 1210.44
  4924.9 1208.92  4947.7 1205.45  4962.1 1203.90  4968.5 1202.12  4989.3 1198.87
  4996.8 1196.26  5002.5 1196.26  5006.1 1194.72  5006.6 1194.22  5013.4 1194.22
  5013.9 1194.72  5030.4 1198.31  5048.5 1201.51  5053.6 1201.31  5091.3 1205.20
  5101.5 1205.54  5107.3 1206.63  5112.3 1206.33  5121.8 1207.29  5142.1 1210.81
  5152.3 1213.39  5161.0 1214.66  5166.1 1213.95  5172.6 1215.79  5192.9 1218.26
#Mann=3,-1,0
  4861.5    0.05       0  5006.1    0.05       0  5013.9    0.05       0
Bank Sta=5006.1,5013.9
Exp/Cntr=0.3,0.1

Type RM Length L Ch R = 1,21207,430,430,430
BEGIN DESCRIPTION:
BEDFORD CREEK 45.0
END DESCRIPTION:
XS GIS Cut Line= 3
      2854705.67     10206603.14      2854737.75     10206506.00
      2854655.69     10206353.13
#Sta/Elev= 30
  4897.7 1208.81  4900.4 1208.81  4908.3 1206.36  4913.6 1202.91  4918.9 1203.38
  4929.3 1199.06  4945.3 1193.72  4971.4 1191.71  4977.1 1189.71  4982.4 1190.26
  4988.6 1189.29  4989.1 1188.79  4996.0 1188.79  4996.5 1189.29  4998.9 1192.40
  5011.9 1192.81  5026.0 1194.04  5033.9 1195.83  5039.5 1195.88  5055.8 1198.40
  5061.5 1198.35  5083.4 1201.33  5105.4 1203.13  5115.9 1203.31  5128.1 1204.89
  5143.5 1205.67  5159.7 1208.07  5165.4 1208.07  5170.7 1209.40  5173.5 1209.40
#Mann=3,-1,0
  4897.7    0.12       0  4988.6    0.07       0  4996.5    0.12       0
Bank Sta=4988.6,4996.5
Exp/Cntr=0.3,0.1

Type RM Length L Ch R = 1,20777,469,469,469
BEGIN DESCRIPTION:
BEDFORD CREEK 44.0
END DESCRIPTION:
XS GIS Cut Line= 3
      2855155.68     10206753.09      2855140.50     10206471.00
      2855055.69     10206153.12
#Sta/Elev= 30
  4717.5 1219.23  4747.5 1212.92  4794.5 1199.52  4811.6 1197.37  4894.8 1180.63
  4917.8 1176.84  4998.3 1178.48  5008.2 1176.97  5018.5 1177.56  5036.1 1185.28
  5049.6 1185.80  5081.3 1183.06  5111.1 1176.59  5116.2 1178.24  5151.2 1171.51
  5156.3 1173.28  5163.4 1170.55  5191.3 1165.51  5196.4 1167.50  5211.2 1164.13
  5211.7 1163.63  5219.1 1164.13  5246.2 1168.66  5266.3 1176.78  5271.5 1176.02
  5298.0 1188.44  5306.4 1194.93  5311.5 1195.04  5326.4 1208.83  5329.0 1208.83
#Mann=5,-1,0
  4717.5    0.05       0  4794.5    0.12       0  4894.8    0.05       0
  5211.2    0.05       0  5219.1    0.05       0
Bank Sta=5211.2,5219.1
Exp/Cntr=0.3,0.1

Type RM Length L Ch R = 1,20308,470,470,470
BEGIN DESCRIPTION:
BEDFORD CREEK 43.0
END DESCRIPTION:
XS GIS Cut Line= 3
      2855555.66     10206603.07      2855529.25     10206552.00
      2855455.66     10206453.07
#Sta/Elev= 30
  4942.5 1162.32  4945.3 1162.32  4950.7 1155.04  4956.3 1150.85  4965.0 1141.47
  4972.9 1131.40  4978.5 1128.68  4987.5 1124.14  5002.4 1123.93  5005.6 1123.56
  5006.1 1123.06  5013.0 1123.06  5013.5 1123.56  5015.8 1125.59  5023.5 1127.30
  5030.4 1127.43  5036.7 1131.49  5045.0 1129.61  5051.3 1139.80  5059.7 1142.37
  5065.9 1144.02  5073.4 1142.81  5080.5 1141.99  5086.7 1145.96  5095.1 1147.03
  5101.3 1153.02  5109.7 1155.88  5115.9 1164.19  5120.1 1163.55  5123.3 1163.55
#Mann=3,-1,0
  4942.5    0.12       0  5005.6    0.07       0  5013.5    0.12       0
Bank Sta=5005.6,5013.5
Exp/Cntr=0.3,0.1

Type RM Length L Ch R = 1,19838,426,426,426
BEGIN DESCRIPTION:
BEDFORD CREEK 42.0
END DESCRIPTION:
XS GIS Cut Line= 3
      2855905.66     10206253.09      2855823.25     10206189.00
      2855405.65     10205903.09
#Sta/Elev= 30
  4895.6 1124.34  4931.8 1121.86  4958.9 1109.38  4977.3 1107.07  4977.8 1106.57
  4985.8 1107.07  5000.0 1107.51  5002.3 1109.83  5012.0 1111.47  5032.2 1119.24
  5038.2 1117.83  5053.1 1119.16  5059.2 1115.51  5068.0 1116.33  5074.1 1114.85
  5095.1 1116.67  5124.9 1119.81  5131.0 1122.04  5139.8 1121.76  5145.9 1124.93
  5160.8 1123.65  5166.8 1126.45  5211.6 1133.49  5217.6 1132.93  5312.1 1144.06
  5348.5 1152.27  5361.1 1157.73  5456.7 1182.20  5469.7 1187.08  5506.1 1193.52
#Mann=4,-1,0
  4895.6    0.12       0  4977.3    0.07       0  4985.8    0.12       0
  5012.0    0.05       0
Bank Sta=4977.3,4985.8
Exp/Cntr=0.3,0.1

Type RM Length L Ch R = 1,19412,362,362,362
BEGIN DESCRIPTION:
BEDFORD CREEK 41.0
END DESCRIPTION:
XS GIS Cut Line= 3
      2856205.69     10206103.12      2856196.50     10205991.00
      2856105.67     10205903.10
#Sta/Elev= 30
  4887.5 1118.47  4890.0 1118.47  4897.5 1117.49  4907.6 1117.13  4917.6 1116.19
  4927.6 1115.50  4950.7 1109.08  4957.7 1106.36  4967.8 1104.62  4977.8 1103.35
  4987.8 1103.05  4992.1 1101.99  4992.6 1101.49  5000.2 1101.49  5000.7 1101.99
  5006.1 1102.36  5013.3 1103.72  5020.3 1108.41  5027.5 1112.35  5034.4 1115.53
  5041.6 1116.88  5048.6 1117.90  5054.6 1117.58  5062.7 1117.54  5069.9 1117.98
  5076.9 1118.16  5084.1 1118.73  5098.2 1119.12  5105.2 1118.79  5126.4 1119.54
#Mann=4,-1,0
  4887.5    0.12       0  4992.1    0.07       0  5000.7    0.12       0
  5054.6    0.05       0
Bank Sta=4992.1,5000.7
Exp/Cntr=0.3,0.1

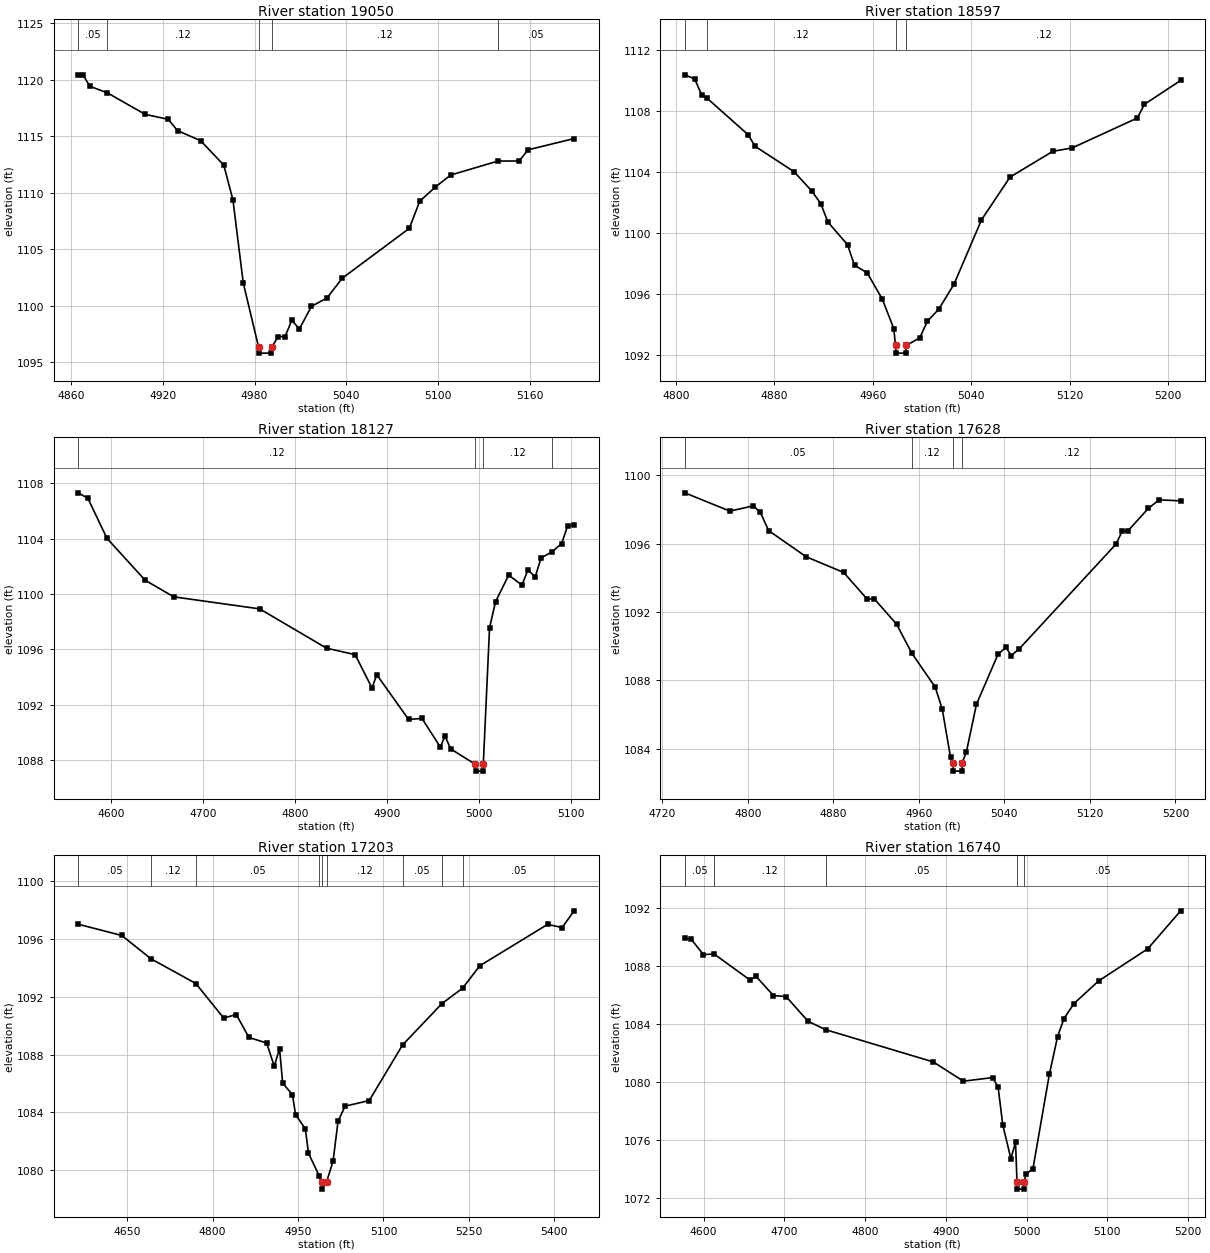
Type RM Length L Ch R = 1,19050,453,453,453
BEGIN DESCRIPTION:
BEDFORD CREEK 40.0
END DESCRIPTION:
XS GIS Cut Line= 3
      2856555.70     10205803.12      2856442.75     10205729.00
      2856255.73     10205703.12
#Sta/Elev= 30
  4864.9 1120.44  4867.9 1120.44  4872.5 1119.42  4883.8 1118.85  4908.6 1116.94
  4923.7 1116.50  4929.7 1115.50  4944.8 1114.61  4959.9 1112.45  4965.9 1109.37
  4972.6 1102.05  4982.7 1096.31  4983.2 1095.81  4990.8 1095.81  4991.3 1096.31
  4995.3 1097.28  5000.0 1097.28  5004.3 1098.72  5009.3 1097.95  5017.2 1099.95
  5027.3 1100.69  5037.4 1102.45  5081.1 1106.85  5087.9 1109.25  5098.0 1110.49
  5108.1 1111.57  5139.1 1112.81  5152.9 1112.81  5158.6 1113.80  5188.8 1114.80
#Mann=5,-1,0
  4864.9    0.05       0  4883.8    0.12       0  4982.7    0.07       0
  4991.3    0.12       0  5139.1    0.05       0
Bank Sta=4982.7,4991.3
Exp/Cntr=0.3,0.1

Type RM Length L Ch R = 1,18597,470,470,470
BEGIN DESCRIPTION:
BEDFORD CREEK 39.0
END DESCRIPTION:
XS GIS Cut Line= 3
      2856755.67     10205503.09      2856661.25     10205335.00
      2856555.69     10205153.11
#Sta/Elev= 30
  4807.2 1110.35  4815.2 1110.08  4820.9 1109.05  4825.3 1108.82  4858.5 1106.44
  4864.5 1105.66  4896.1 1104.00  4910.4 1102.74  4917.8 1101.91  4923.5 1100.71
  4939.5 1099.22  4945.2 1097.87  4955.4 1097.39  4967.8 1095.65  4977.1 1093.73
  4978.5 1092.62  4979.0 1092.12  4986.7 1092.12  4987.2 1092.62  4998.2 1093.12
  5004.5 1094.22  5013.7 1095.00  5026.1 1096.64  5048.4 1100.85  5071.6 1103.65
  5106.4 1105.34  5122.1 1105.56  5175.1 1107.52  5180.9 1108.42  5210.3 1109.98
#Mann=4,-1,0
  4807.2    0.05       0  4825.3    0.12       0  4978.5    0.07       0
  4987.2    0.12       0
Bank Sta=4978.5,4987.2
Exp/Cntr=0.3,0.1

Type RM Length L Ch R = 1,18127,499,499,499
BEGIN DESCRIPTION:
BEDFORD CREEK 38.0
END DESCRIPTION:
XS GIS Cut Line= 3
      2856855.68     10205403.13      2856970.75     10204983.00
      2856905.70     10204903.14
#Sta/Elev= 30
  4564.4 1107.31  4574.8 1106.91  4595.5 1104.02  4637.0 1100.99  4668.1 1099.79
  4761.4 1098.92  4834.0 1096.08  4865.1 1095.61  4883.4 1093.20  4888.6 1094.16
  4923.1 1090.93  4937.7 1091.00  4957.6 1088.93  4962.7 1089.73  4968.8 1088.80
  4995.5 1087.69  4996.0 1087.19  5003.8 1087.19  5004.3 1087.69  5011.1 1097.55
  5017.6 1099.44  5031.9 1101.36  5046.3 1100.64  5052.8 1101.74  5060.7 1101.23
  5067.1 1102.61  5078.4 1103.02  5089.4 1103.64  5095.8 1104.90  5103.0 1104.99
#Mann=4,-1,0
  4564.4    0.12       0  4995.5    0.07       0  5004.3    0.12       0
  5078.4    0.05       0
Bank Sta=4995.5,5004.3
Exp/Cntr=0.3,0.1

Type RM Length L Ch R = 1,17628,425,425,425
BEGIN DESCRIPTION:
BEDFORD CREEK 37.0
END DESCRIPTION:
XS GIS Cut Line= 3
      2857155.70     10205453.09      2857324.75     10205257.00
      2857305.68     10205053.09
#Sta/Elev= 30
  4741.1 1098.97  4783.3 1097.90  4805.2 1098.21  4811.8 1097.82  4819.5 1096.76
  4854.6 1095.23  4889.7 1094.31  4911.7 1092.75  4918.3 1092.77  4939.1 1091.29
  4953.4 1089.59  4975.3 1087.60  4981.9 1086.31  4989.6 1083.50  4991.8 1083.19
  4992.3 1082.69  5000.1 1082.69  5000.6 1083.19  5004.5 1083.83  5013.9 1086.61
  5034.0 1089.52  5041.4 1089.93  5046.4 1089.45  5054.1 1089.86  5144.5 1095.98
  5150.3 1096.75  5155.3 1096.73  5174.6 1098.06  5184.7 1098.56  5204.8 1098.50
#Mann=4,-1,0
  4741.1    0.05       0  4953.4    0.12       0  4991.8    0.07       0
  5000.6    0.12       0
Bank Sta=4991.8,5000.6
Exp/Cntr=0.3,0.1

Type RM Length L Ch R = 1,17203,463,463,463
BEGIN DESCRIPTION:
BEDFORD CREEK 36.0
END DESCRIPTION:
XS GIS Cut Line= 3
      2857305.65     10205603.13      2857698.50     10205414.00
      2857555.68     10205003.11
#Sta/Elev= 30
  4564.0 1097.03  4640.4 1096.25  4691.4 1094.64  4770.5 1092.92  4819.3 1090.53
  4841.5 1090.77  4863.7 1089.18  4894.9 1088.80  4908.1 1087.19  4917.5 1088.40
  4923.0 1086.01  4940.1 1085.22  4945.7 1083.82  4962.7 1082.86  4968.3 1081.16
  4987.2 1079.58  4991.2 1079.17  4991.7 1078.67  5000.1 1079.17  5011.5 1080.61
  5020.3 1083.40  5032.7 1084.42  5075.0 1084.81  5133.5 1088.66  5202.7 1091.53
  5239.1 1092.60  5269.2 1094.15  5388.3 1097.02  5413.8 1096.80  5435.0 1097.96
#Mann=9,-1,0
  4564.0    0.05       0  4691.4    0.12       0  4770.5    0.05       0
  4987.2    0.12       0  4991.2    0.07       0  5000.1    0.12       0
  5133.5    0.05       0  5202.7    0.12       0  5239.1    0.05       0
Bank Sta=4991.2,5000.1
Exp/Cntr=0.3,0.1

Type RM Length L Ch R = 1,16740,413,413,413
BEGIN DESCRIPTION:
BEDFORD CREEK 35.0
END DESCRIPTION:
XS GIS Cut Line= 3
      2857755.68     10205803.11      2858122.00     10205591.00
      2858155.69     10205403.10
#Sta/Elev= 30
  4576.7 1089.93  4584.6 1089.86  4599.8 1088.80  4613.0 1088.84  4657.6 1087.04
  4664.9 1087.30  4686.5 1085.97  4702.2 1085.90  4729.5 1084.19  4751.5 1083.61
  4884.5 1081.39  4921.8 1080.06  4958.0 1080.31  4964.8 1079.66  4970.6 1077.04
  4980.6 1074.72  4986.4 1075.83  4988.2 1073.11  4988.7 1072.61  4996.7 1072.61
  4997.2 1073.11  4999.2 1073.63  5008.0 1074.03  5028.3 1080.54  5038.5 1083.14
  5046.4 1084.38  5058.8 1085.42  5089.3 1086.98  5150.2 1089.20  5190.9 1091.82
#Mann=5,-1,0
  4576.7    0.05       0  4613.0    0.12       0  4751.5    0.05       0
  4988.2    0.03       0  4997.2    0.05       0
Bank Sta=4988.2,4997.2
Exp/Cntr=0.3,0.1

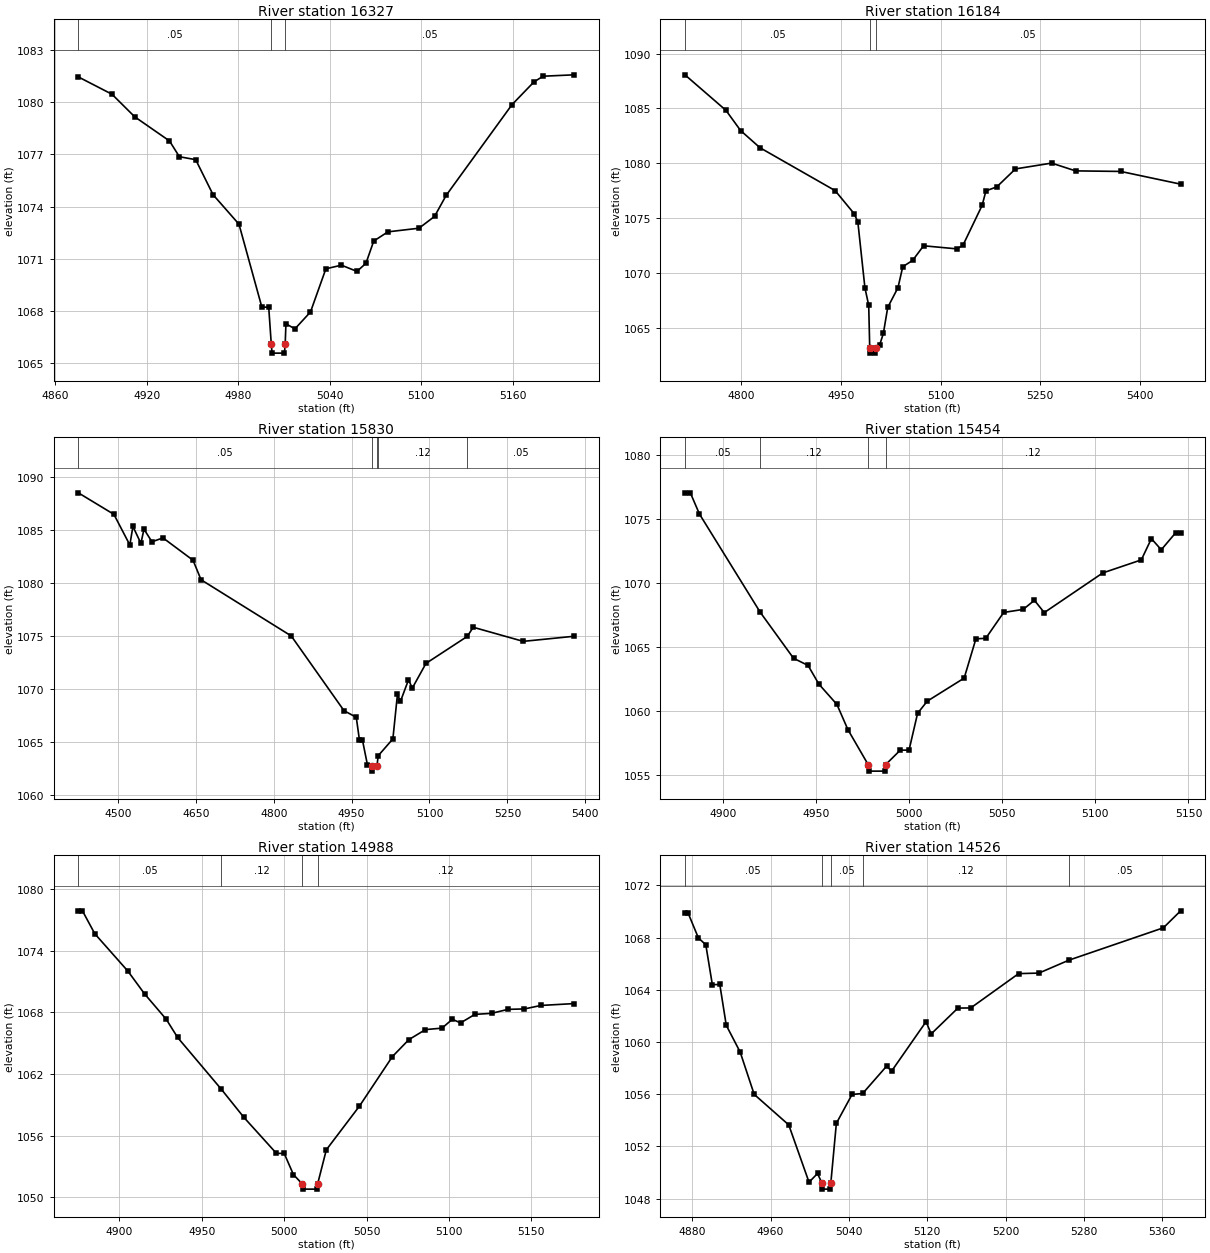
Type RM Length L Ch R = 1,16327,143,143,143
BEGIN DESCRIPTION:
BEDFORD CREEK 34.0
END DESCRIPTION:
XS GIS Cut Line= 3
      2858205.70     10206003.10      2858318.75     10205950.00
      2858355.68     10205753.13
#Sta/Elev= 30
  4875.1 1081.47  4897.2 1080.47  4912.1 1079.17  4934.9 1077.78  4941.4 1076.87
  4952.1 1076.70  4963.5 1074.68  4980.5 1072.98  4995.5 1068.20  5000.0 1068.20
  5001.7 1066.05  5002.2 1065.55  5010.3 1065.55  5010.8 1066.05  5011.3 1067.24
  5017.2 1066.95  5027.4 1067.92  5037.5 1070.41  5047.7 1070.62  5057.9 1070.26
  5063.8 1070.73  5068.9 1072.01  5078.2 1072.54  5098.6 1072.75  5108.8 1073.43
  5116.4 1074.64  5159.6 1079.87  5174.0 1081.18  5180.0 1081.51  5200.3 1081.59
#Mann=3,-1,0
  4875.1    0.05       0  5001.7    0.05       0  5010.8    0.05       0
Bank Sta=5001.7,5010.8
Exp/Cntr=0.3,0.1

Type RM Length L Ch R = 1,16184,354,354,354
BEGIN DESCRIPTION:
Mapping XS 6616ceb2
END DESCRIPTION:
XS GIS Cut Line= 2
      2858302.14     10206283.02      2858649.36     10205623.31
#Sta/Elev= 30
  4715.5 1088.07  4777.2 1084.83  4799.2 1082.99  4828.4 1081.42  4941.4 1077.51
  4969.8 1075.42  4975.5 1074.68  4986.2 1068.64  4991.9 1067.05  4993.4 1063.19
  4993.9 1062.69  5002.0 1062.69  5002.5 1063.19  5008.3 1063.43  5013.9 1064.48
  5020.5 1066.86  5035.9 1068.66  5043.1 1070.57  5058.0 1071.15  5074.4 1072.48
  5124.1 1072.20  5133.5 1072.51  5162.5 1076.17  5168.2 1077.49  5184.5 1077.85
  5212.6 1079.49  5267.0 1080.02  5303.0 1079.31  5370.8 1079.26  5461.0 1078.10
#Mann=3,-1,0
  4715.5    0.05       0  4993.4    0.03       0  5002.5    0.05       0
Bank Sta=4993.4,5002.5
Exp/Cntr=0.3,0.1

Type RM Length L Ch R = 1,15830,376,376,376
BEGIN DESCRIPTION:
Mapping XS a0d021f7
END DESCRIPTION:
XS GIS Cut Line= 3
      2858475.76     10206578.15      2858814.30     10206031.28
      2858883.67     10205727.78
#Sta/Elev= 30
  4423.8 1088.53  4492.3 1086.50  4523.0 1083.61  4528.9 1085.36  4544.3 1083.76
  4550.2 1085.10  4565.6 1083.91  4586.8 1084.28  4644.7 1082.17  4660.1 1080.33
  4833.8 1075.03  4935.4 1067.98  4959.0 1067.36  4965.0 1065.25  4970.9 1065.21
  4980.4 1062.90  4989.7 1062.78  4990.2 1062.28  4998.9 1062.78  5001.2 1063.73
  5029.5 1065.32  5038.3 1069.52  5044.1 1068.86  5059.5 1070.88  5067.0 1070.12
  5093.2 1072.44  5172.8 1074.99  5184.2 1075.85  5280.5 1074.52  5378.3 1075.00
#Mann=5,-1,0
  4423.8    0.05       0  4989.7    0.05       0  4998.9    0.05       0
  5001.2    0.12       0  5172.8    0.05       0
Bank Sta=4989.7,4998.9
Exp/Cntr=0.3,0.1

Type RM Length L Ch R = 1,15454,466,466,466
BEGIN DESCRIPTION:
BEDFORD CREEK 32.0
END DESCRIPTION:
XS GIS Cut Line= 3
      2859105.69     10205953.13      2859043.75     10205850.00
      2858905.69     10205803.11
#Sta/Elev= 30
  4879.7 1077.05  4882.6 1077.05  4887.5 1075.39  4920.1 1067.72  4938.0 1064.12
  4945.8 1063.56  4951.6 1062.10  4961.3 1060.51  4967.2 1058.54  4978.1 1055.80
  4978.6 1055.30  4986.9 1055.30  4987.4 1055.80  4995.3 1056.94  5000.0 1056.94
  5004.6 1059.82  5009.8 1060.77  5029.6 1062.57  5035.9 1065.64  5041.2 1065.68
  5050.8 1067.70  5061.3 1067.94  5067.3 1068.65  5072.6 1067.69  5104.0 1070.79
  5124.7 1071.81  5130.1 1073.47  5135.4 1072.60  5143.2 1073.94  5145.8 1073.94
#Mann=4,-1,0
  4879.7    0.05       0  4920.1    0.12       0  4978.1    0.07       0
  4987.4    0.12       0
Bank Sta=4978.1,4987.4
Exp/Cntr=0.3,0.1

Type RM Length L Ch R = 1,14988,462,462,462
BEGIN DESCRIPTION:
BEDFORD CREEK 31.0
END DESCRIPTION:
XS GIS Cut Line= 3
      2859455.66     10205503.11      2859331.25     10205491.00
      2859155.67     10205503.11
#Sta/Elev= 30
  4875.0 1077.88  4877.5 1077.88  4885.0 1075.65  4905.1 1072.01  4915.2 1069.80
  4928.4 1067.32  4935.3 1065.55  4961.9 1060.50  4975.5 1057.78  4995.3 1054.27
  5000.0 1054.27  5005.6 1052.21  5011.0 1051.29  5011.5 1050.79  5019.8 1050.79
  5020.3 1051.29  5025.6 1054.62  5045.7 1058.87  5065.7 1063.69  5075.7 1065.34
  5085.8 1066.32  5095.8 1066.46  5102.1 1067.32  5107.1 1066.97  5115.8 1067.80
  5125.9 1067.90  5135.9 1068.29  5145.9 1068.33  5155.9 1068.67  5176.0 1068.85
#Mann=4,-1,0
  4875.0    0.05       0  4961.9    0.12       0  5011.0    0.07       0
  5020.3    0.12       0
Bank Sta=5011,5020.3
Exp/Cntr=0.3,0.1

Type RM Length L Ch R = 1,14526,454,454,454
BEGIN DESCRIPTION:
BEDFORD CREEK 30.0
END DESCRIPTION:
XS GIS Cut Line= 3
      2859555.66     10205153.08      2859472.00     10205057.00
      2859105.70     10205153.11
#Sta/Elev= 30
  4872.6 1069.87  4875.9 1069.87  4886.3 1067.98  4893.9 1067.45  4900.6 1064.39
  4908.2 1064.41  4914.8 1061.28  4929.0 1059.23  4943.3 1055.99  4978.6 1053.65
  4999.3 1049.26  5008.0 1049.93  5012.2 1049.23  5012.7 1048.73  5021.1 1048.73
  5021.6 1049.23  5027.2 1053.77  5043.2 1055.98  5054.1 1056.06  5078.5 1058.15
  5083.6 1057.77  5118.8 1061.56  5124.0 1060.62  5151.3 1062.60  5164.4 1062.61
  5213.3 1065.24  5234.0 1065.28  5264.6 1066.27  5361.1 1068.75  5378.7 1070.05
#Mann=5,-1,0
  4872.6    0.05       0  5012.2    0.05       0  5021.6    0.05       0
  5054.1    0.12       0  5264.6    0.05       0
Bank Sta=5012.2,5021.6
Exp/Cntr=0.3,0.1

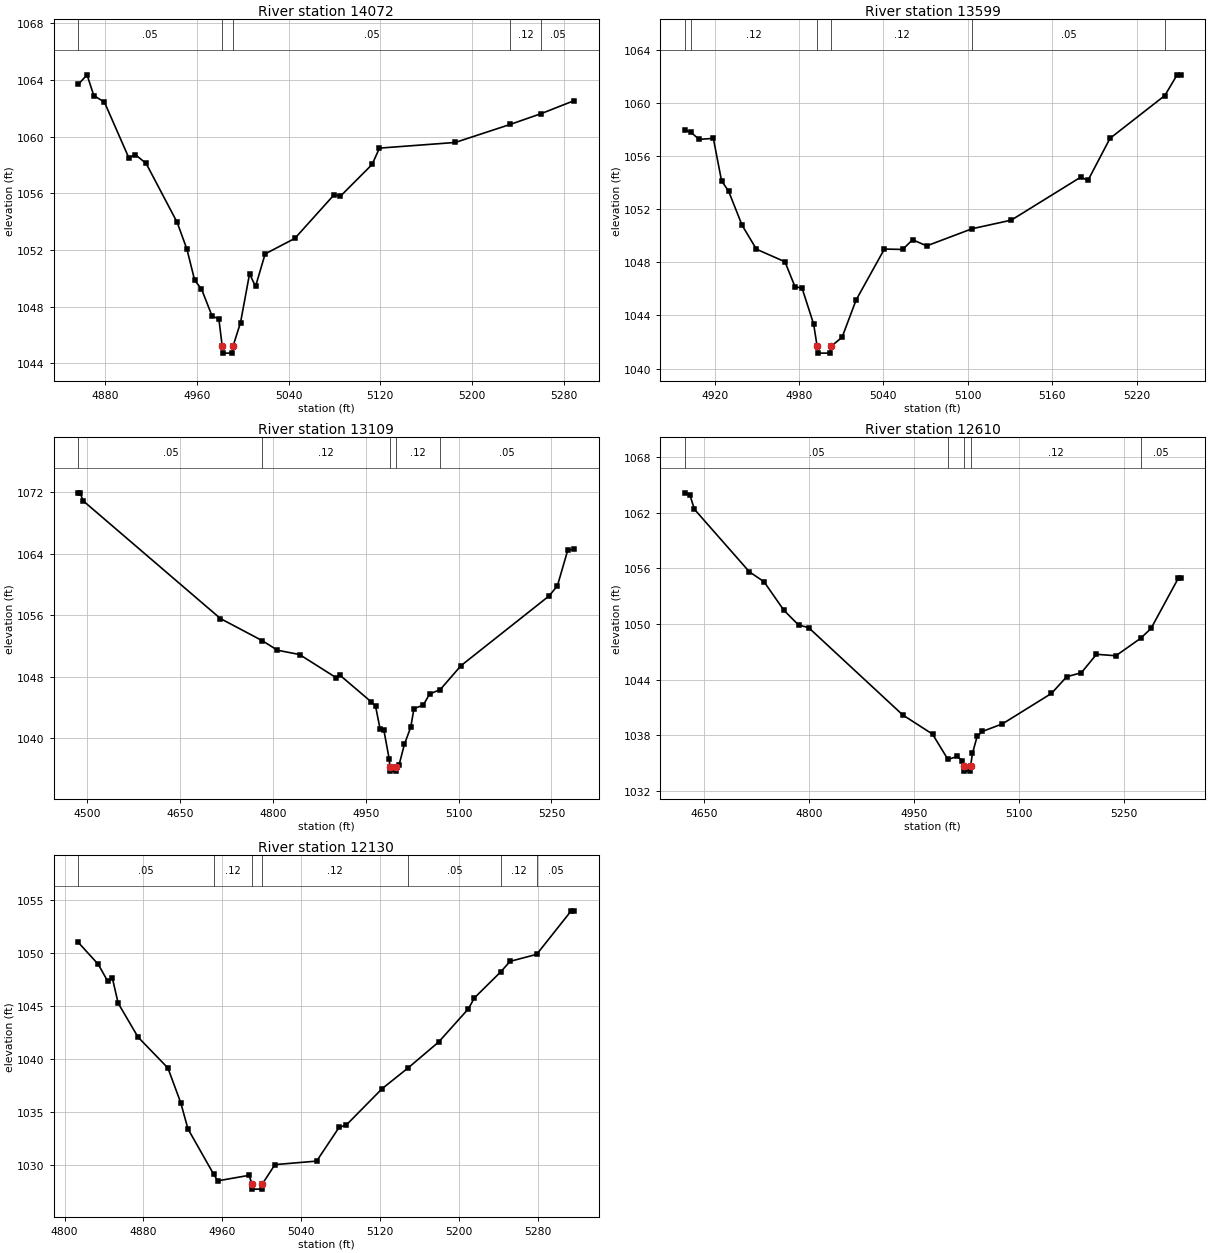
Type RM Length L Ch R = 1,14072,473,473,473
BEGIN DESCRIPTION:
BEDFORD CREEK 29.0
END DESCRIPTION:
XS GIS Cut Line= 3
      2859705.65     10204703.09      2859584.50     10204626.00
      2859305.67     10204703.12
#Sta/Elev= 30
  4856.4 1063.69  4864.0 1064.36  4869.9 1062.90  4879.2 1062.43  4900.4 1058.52
  4906.3 1058.72  4915.6 1058.11  4942.7 1053.95  4951.2 1052.06  4958.0 1049.86
  4963.9 1049.26  4973.2 1047.34  4979.1 1047.14  4982.0 1045.23  4982.5 1044.73
  4991.0 1044.73  4991.5 1045.23  4998.0 1046.88  5005.9 1050.33  5011.1 1049.43
  5019.5 1051.73  5045.4 1052.82  5079.8 1055.91  5085.0 1055.78  5112.9 1058.04
  5119.3 1059.19  5185.5 1059.59  5233.4 1060.86  5260.7 1061.63  5289.3 1062.54
#Mann=5,-1,0
  4856.4    0.05       0  4982.0    0.05       0  4991.5    0.05       0
  5233.4    0.12       0  5260.7    0.05       0
Bank Sta=4982,4991.5
Exp/Cntr=0.3,0.1

Type RM Length L Ch R = 1,13599,490,490,490
BEGIN DESCRIPTION:
BEDFORD CREEK 28.0
END DESCRIPTION:
XS GIS Cut Line= 3
      2859755.67     10204153.11      2859656.25     10204172.00
      2859405.66     10204153.11
#Sta/Elev= 30
  4898.8 1057.99  4903.1 1057.82  4909.0 1057.28  4919.1 1057.36  4924.9 1054.17
  4930.0 1053.36  4939.5 1050.81  4949.7 1049.00  4970.0 1048.05  4977.1 1046.18
  4982.2 1046.05  4990.4 1043.35  4992.9 1041.66  4993.4 1041.16  5002.1 1041.16
  5002.6 1041.66  5010.6 1042.35  5020.6 1045.17  5040.7 1049.01  5053.7 1048.98
  5060.7 1049.71  5070.8 1049.25  5103.0 1050.54  5130.9 1051.19  5180.4 1054.44
  5185.4 1054.18  5201.1 1057.36  5240.1 1060.59  5248.8 1062.15  5251.3 1062.15
#Mann=6,-1,0
  4898.8    0.05       0  4903.1    0.12       0  4992.9    0.07       0
  5002.6    0.12       0  5103.0    0.05       0  5240.1    0.12       0
Bank Sta=4992.9,5002.6
Exp/Cntr=0.3,0.1

Type RM Length L Ch R = 1,13109,499,499,499
BEGIN DESCRIPTION:
BEDFORD CREEK 27.0
END DESCRIPTION:
XS GIS Cut Line= 3
      2860105.67     10204003.10      2859688.00     10203703.00
      2859405.67     10203653.11
#Sta/Elev= 30
  4485.7 1071.92  4488.8 1071.92  4493.0 1070.91  4715.3 1055.55  4783.1 1052.66
  4807.4 1051.43  4843.0 1050.87  4901.9 1047.87  4908.0 1048.20  4958.4 1044.74
  4965.9 1044.13  4973.1 1041.19  4979.2 1041.06  4987.8 1037.31  4989.1 1036.19
  4989.6 1035.69  4998.3 1035.69  4998.8 1036.19  5003.7 1036.45  5012.5 1039.19
  5022.7 1041.42  5027.9 1043.83  5043.0 1044.29  5053.1 1045.72  5070.4 1046.31
  5103.9 1049.42  5246.1 1058.49  5259.6 1059.81  5276.5 1064.50  5286.7 1064.56
#Mann=5,-1,0
  4485.7    0.05       0  4783.1    0.12       0  4989.1    0.07       0
  4998.8    0.12       0  5070.4    0.05       0
Bank Sta=4989.1,4998.8
Exp/Cntr=0.3,0.1

Type RM Length L Ch R = 1,12610,480,480,480
BEGIN DESCRIPTION:
BEDFORD CREEK 26.0
END DESCRIPTION:
XS GIS Cut Line= 3
      2860255.67     10203653.10      2860003.25     10203372.00
      2859755.65     10203153.08
#Sta/Elev= 30
  4622.2 1064.13  4629.3 1063.93  4636.0 1062.35  4714.5 1055.61  4735.4 1054.54
  4763.8 1051.46  4784.8 1049.87  4799.0 1049.60  4933.5 1040.18  4976.1 1038.11
  4998.1 1035.38  5011.3 1035.70  5018.9 1035.24  5020.6 1034.62  5021.1 1034.12
  5029.9 1034.12  5030.4 1034.62  5033.1 1036.03  5039.8 1037.86  5047.3 1038.40
  5075.8 1039.21  5146.0 1042.50  5167.8 1044.30  5188.7 1044.73  5210.3 1046.72
  5238.0 1046.56  5273.3 1048.44  5288.2 1049.50  5327.1 1054.91  5330.5 1054.91
#Mann=5,-1,0
  4622.2    0.05       0  4998.1    0.12       0  5020.6    0.07       0
  5030.4    0.12       0  5273.3    0.05       0
Bank Sta=5020.6,5030.4
Exp/Cntr=0.3,0.1

Type RM Length L Ch R = 1,12130,484,484,484
BEGIN DESCRIPTION:
BEDFORD CREEK 25.0
END DESCRIPTION:
XS GIS Cut Line= 3
      2860455.68     10203353.07      2860428.25     10203169.00
      2860255.67     10202903.09
#Sta/Elev= 30
  4813.9 1050.97  4834.1 1048.91  4843.5 1047.35  4848.5 1047.59  4854.3 1045.25
  4874.5 1042.05  4904.8 1039.14  4917.8 1035.87  4925.1 1033.41  4951.1 1029.15
  4955.4 1028.51  4987.1 1029.03  4990.1 1028.23  4990.6 1027.73  5000.2 1027.73
  5000.7 1028.23  5013.4 1030.04  5055.7 1030.37  5078.5 1033.55  5085.9 1033.78
  5122.2 1037.20  5148.4 1039.14  5179.5 1041.59  5209.7 1044.72  5215.8 1045.75
  5242.4 1048.19  5252.0 1049.19  5279.0 1049.85  5314.0 1053.95  5317.0 1053.95
#Mann=7,-1,0
  4813.9    0.05       0  4951.1    0.12       0  4990.1    0.07       0
  5000.7    0.12       0  5148.4    0.05       0  5242.4    0.12       0
  5279.0    0.05       0
Bank Sta=4990.1,5000.7
Exp/Cntr=0.3,0.1