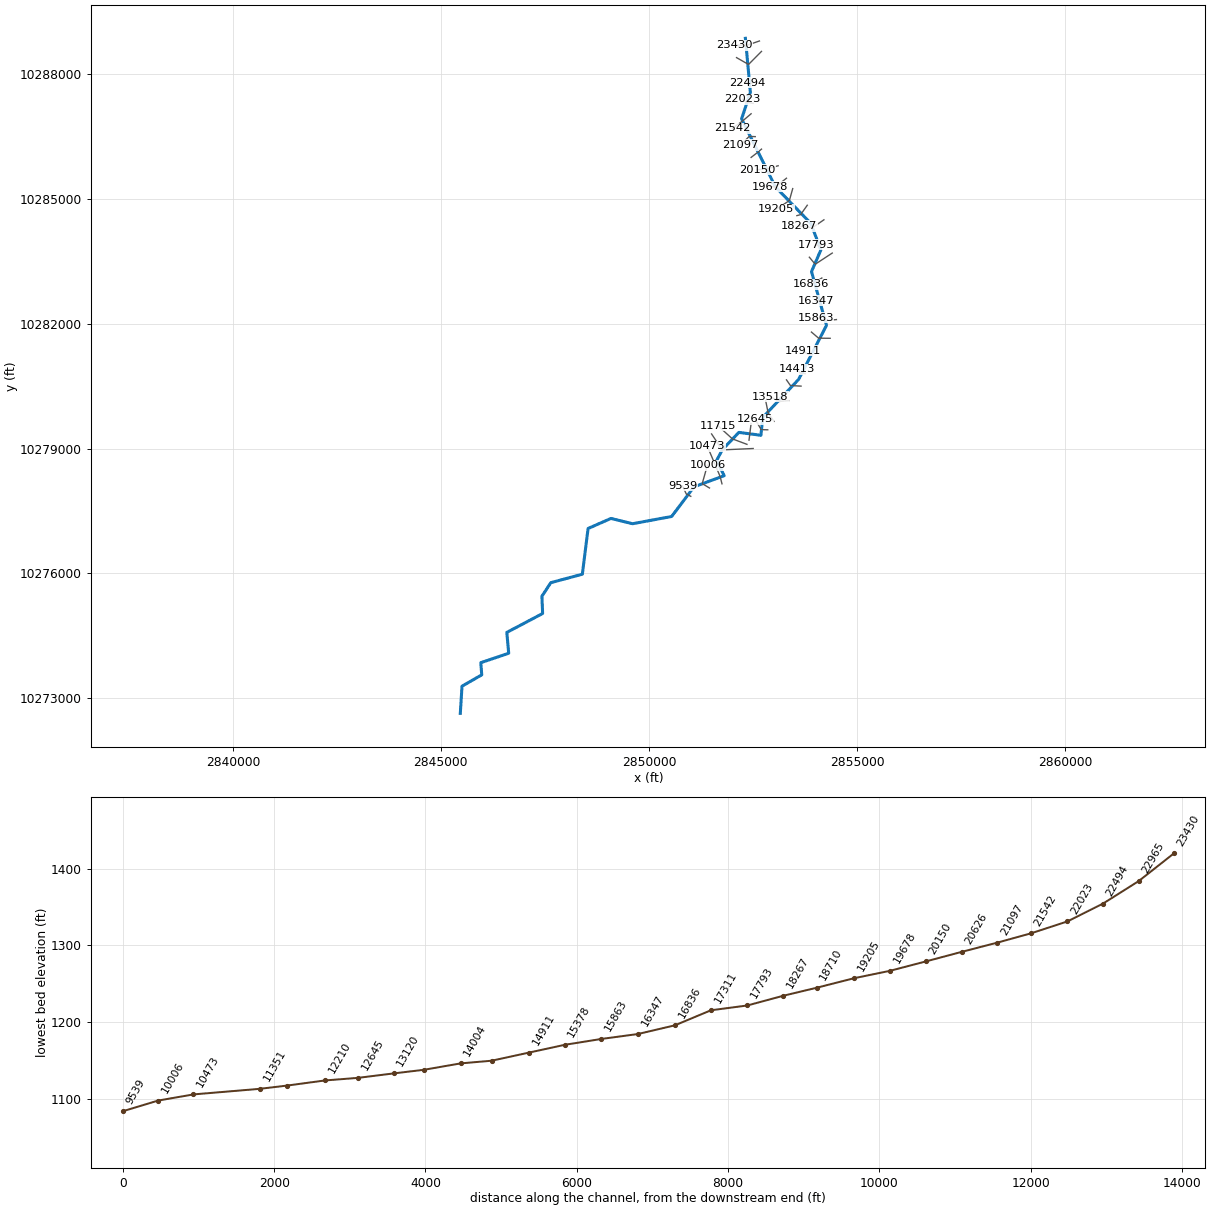
--- CEDAR HOLLOW CREEK.prj (project) ---

Proj Title=CEDAR HOLLOW CREEK Base Level Engineering
Current Plan=p01
Default Exp/Contr=0.3,0.1
English Units
Geom File=g01
Flow File=f01
Plan File=p01
BEGIN DESCRIPTION:
CEDAR HOLLOW CREEK
END DESCRIPTION:

--- CEDAR HOLLOW CREEK.p01 (plan) ---

Plan Title=Multiple Run
Short Identifier=Multiple
Geom File=g01
Flow File=f01
Subcritical Flow
K Sum by GR= 0
Std Step Tol= 0.01
Critical Tol= 0.01
Num of Std Step Trials= 20
Max Error Tol= 0.3
Flow Tol Ratio= 0.001
Split Flow NTrial= 30
Split Flow Tol= 0.02
Split Flow Ratio= 0.02
Log Output Level= 0
Friction Slope Method= 1
Unsteady Friction Slope Method= 2
Unsteady Bridges Friction Slope Method= 1
Parabolic Critical Depth
Global Vel Dist=  1 , 1 , 1
Global Log Level= 0
CheckData=True
Encroach Param= -1, 0, 0, 0
BEGIN DESCRIPTION:
Multiple Run
END DESCRIPTION:

--- CEDAR HOLLOW CREEK.f01 (steady flow) ---

Flow Title=Multiple
Number of Profiles=7
Profile Names=10-year,25-year,50-year,1pct_min,100-year,1pct_plu,500-year
River Rch & RM= CEDAR HOLLOW CRE,Reach-1,23430
     427     686    1911    1695    2771    4530    4147
River Rch & RM= CEDAR HOLLOW CRE,Reach-1,16347
     713    1189    3069    2481    4488    8116    6650
River Rch & RM= CEDAR HOLLOW CRE,Reach-1,10473
     846    1431    3524    2737    5161    9733    7623
River Rch & RM= CEDAR HOLLOW CRE,Reach-1,7299
     952    1618    4146    3267    6106   11413    9004
River Rch & RM= CEDAR HOLLOW CRE,Reach-1,6847
    1139    1965    4786    3635    7056   13698   10356
River Rch & RM= CEDAR HOLLOW CRE,Reach-1,2747
    1392    2429    5965    4502    8840   17359   12920
Boundary for River Rch & Prof#=CEDAR HOLLOW CRE,Reach-1,1
Up Type=0
Dn Type=3
Dn Slope=0.005
Boundary for River Rch & Prof#=CEDAR HOLLOW CRE,Reach-1,2
Up Type=0
Dn Type=3
Dn Slope=0.005
Boundary for River Rch & Prof#=CEDAR HOLLOW CRE,Reach-1,3
Up Type=0
Dn Type=3
Dn Slope=0.005
Boundary for River Rch & Prof#=CEDAR HOLLOW CRE,Reach-1,4
Up Type=0
Dn Type=3
Dn Slope=0.005
Boundary for River Rch & Prof#=CEDAR HOLLOW CRE,Reach-1,5
Up Type=0
Dn Type=3
Dn Slope=0.005
Boundary for River Rch & Prof#=CEDAR HOLLOW CRE,Reach-1,6
Up Type=0
Dn Type=3
Dn Slope=0.005
Boundary for River Rch & Prof#=CEDAR HOLLOW CRE,Reach-1,7
Up Type=0
Dn Type=3
Dn Slope=0.005

--- CEDAR HOLLOW CREEK.g01 (geometry) ---

Geom Title=Existing Conditions

River Reach=CEDAR HOLLOW CRE,Reach-1
Reach XY= 30
      2852318.50     10288867.00      2852438.50     10287568.00
      2852227.25     10286931.00      2853040.50     10285294.00
      2853895.00     10284412.00      2854131.50     10283775.00
      2853907.50     10283258.00      2854267.25     10281963.00
      2853597.25     10280665.00      2852736.00     10279750.00
      2852691.00     10279321.00      2852161.25     10279390.00
      2851760.25     10278969.00      2851630.00     10278719.00
      2851807.25     10278349.00      2851083.00     10278080.00
      2850545.75     10277368.00      2849607.00     10277194.00
      2849087.50     10277321.00      2848538.00     10277079.00
      2848399.75     10275980.00      2847642.00     10275776.00
      2847428.50     10275450.00      2847445.50     10275035.00
      2846584.75     10274580.00      2846630.25     10274079.00
      2845959.75     10273852.00      2845982.00     10273559.00
      2845508.00     10273287.00      2845467.00     10272633.00

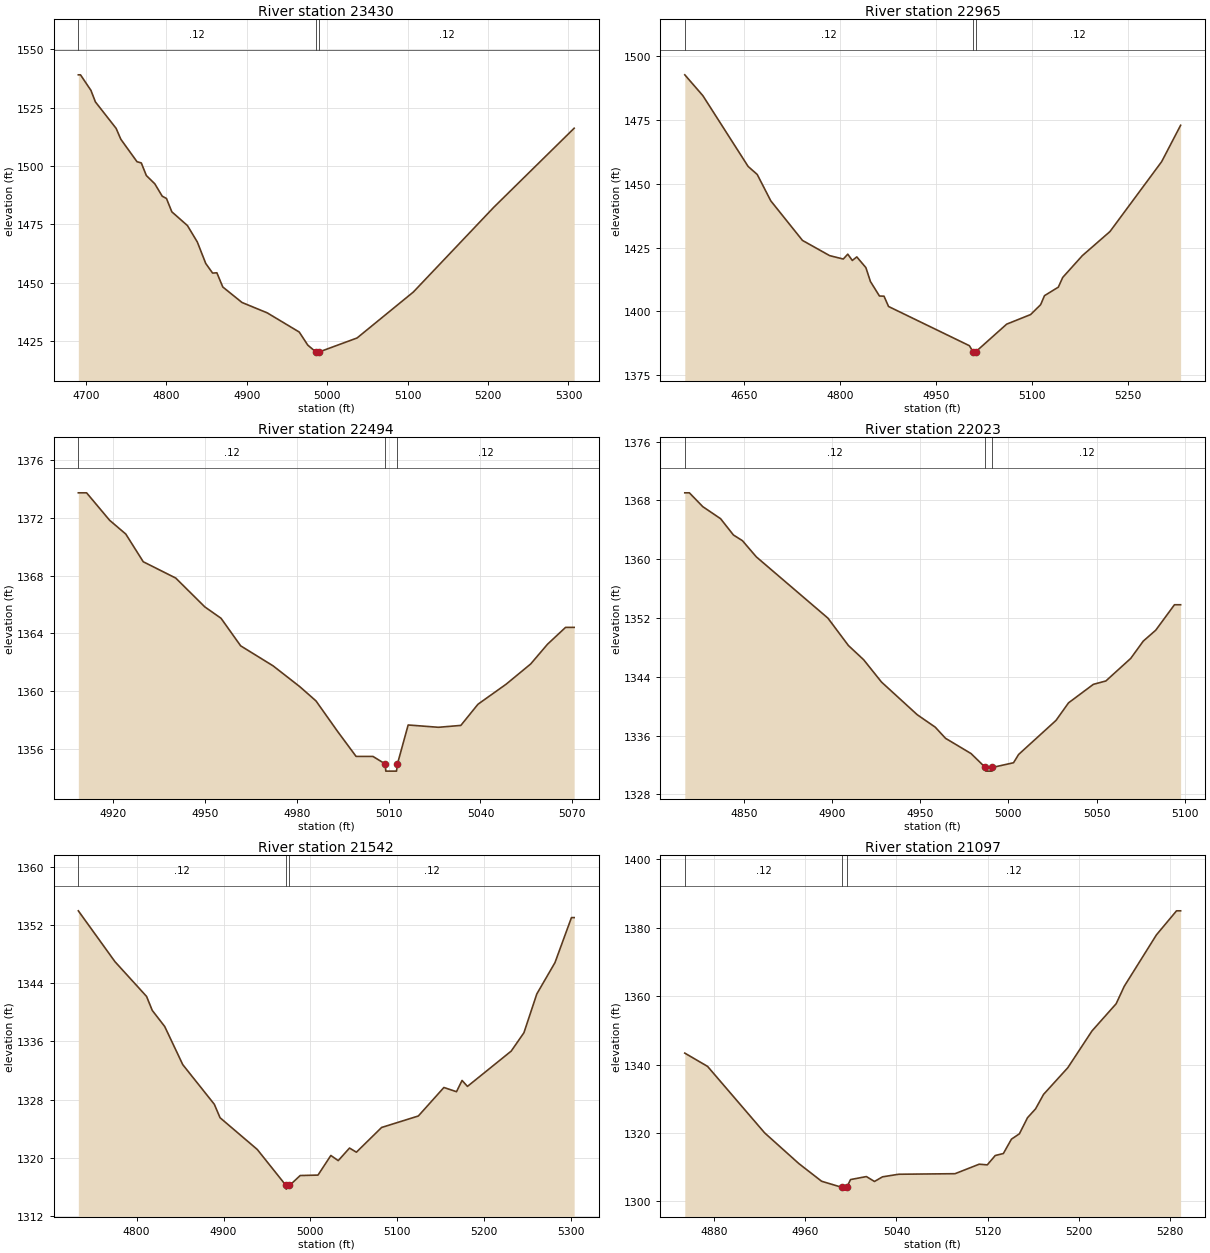
Type RM Length L Ch R = 1,23430,465,465,465
BEGIN DESCRIPTION:
CEDAR HOLLOW CREEK 50.0
END DESCRIPTION:
XS GIS Cut Line= 3
      2852655.71     10288803.12      2852362.75     10288703.00
      2852055.65     10288703.11
#Sta/Elev= 30
  4690.4 1539.00  4693.1 1539.00  4706.1 1532.33  4711.6 1527.42  4737.4 1516.06
  4743.3 1511.38  4763.4 1501.77  4768.7 1501.26  4775.0 1495.85  4785.5 1492.32
  4794.7 1487.03  4800.0 1486.03  4806.7 1480.31  4826.1 1474.42  4838.4 1467.38
  4848.9 1458.17  4857.4 1454.06  4862.7 1454.19  4870.1 1448.10  4894.0 1441.46
  4925.3 1437.03  4965.2 1428.79  4975.8 1423.19  4985.9 1420.27  4986.2 1419.77
  4989.9 1420.27  5037.1 1426.26  5107.1 1445.95  5207.1 1482.24  5307.1 1516.12
#Mann=3,-1,0
  4690.4    0.12       0  4985.9    0.07       0  4989.9    0.12       0
Bank Sta=4985.9,4989.9
Exp/Cntr=0.3,0.1

Type RM Length L Ch R = 1,22965,471,471,471
BEGIN DESCRIPTION:
CEDAR HOLLOW CREEK 49.0
END DESCRIPTION:
XS GIS Cut Line= 3
      2852705.66     10288553.09      2852394.25     10288239.00
      2852105.66     10288403.13
#Sta/Elev= 30
  4557.7 1492.50  4585.9 1484.36  4656.6 1456.69  4670.8 1453.56  4692.0 1443.24
  4741.5 1427.77  4783.9 1421.83  4805.2 1420.50  4812.2 1422.40  4819.3 1419.94
  4826.3 1421.33  4840.5 1417.14  4847.6 1411.71  4861.7 1406.04  4868.8 1405.98
  4875.9 1401.95  5002.1 1386.63  5007.9 1384.22  5008.1 1383.72  5011.9 1384.22
  5060.3 1395.04  5097.7 1398.79  5113.4 1402.66  5119.4 1406.18  5141.0 1409.51
  5147.9 1413.31  5178.5 1421.82  5221.7 1431.25  5302.4 1458.57  5332.0 1472.78
#Mann=3,-1,0
  4557.7    0.12       0  5007.9    0.07       0  5011.9    0.12       0
Bank Sta=5007.9,5011.9
Exp/Cntr=0.3,0.1

Type RM Length L Ch R = 1,22494,471,471,471
BEGIN DESCRIPTION:
CEDAR HOLLOW CREEK 48.0
END DESCRIPTION:
XS GIS Cut Line= 3
      2852505.69     10287803.11      2852419.50     10287773.00
      2852355.65     10287803.13
#Sta/Elev= 28
  4908.7 1373.74  4911.4 1373.74  4918.9 1371.84  4924.2 1370.88  4929.9 1368.96
  4940.5 1367.83  4950.0 1365.83  4955.3 1365.04  4961.7 1363.13  4972.3 1361.74
  4981.0 1360.30  4986.3 1359.31  4993.4 1357.18  4999.4 1355.46  5004.9 1355.46
  5008.9 1354.94  5009.1 1354.44  5012.6 1354.44  5012.9 1354.94  5016.4 1357.64
  5026.3 1357.48  5033.6 1357.61  5039.2 1359.08  5048.4 1360.47  5056.4 1361.87
  5061.9 1363.24  5067.8 1364.41  5070.6 1364.41
#Mann=3,-1,0
  4908.7    0.12       0  5008.9    0.07       0  5012.9    0.12       0
Bank Sta=5008.9,5012.9
Exp/Cntr=0.3,0.1

Type RM Length L Ch R = 1,22023,481,481,481
BEGIN DESCRIPTION:
CEDAR HOLLOW CREEK 47.0
END DESCRIPTION:
XS GIS Cut Line= 3
      2852505.73     10287303.10      2852324.75     10287334.00
      2852255.69     10287403.11
#Sta/Elev= 30
  4816.4 1369.04  4819.0 1369.04  4826.6 1367.16  4836.7 1365.52  4844.0 1363.30
  4849.1 1362.53  4857.0 1360.32  4897.6 1351.99  4909.2 1348.27  4917.9 1346.32
  4928.0 1343.29  4948.3 1338.84  4958.5 1337.15  4964.3 1335.64  4978.8 1333.56
  4986.9 1331.67  4987.2 1331.17  4990.7 1331.17  4990.9 1331.67  5002.9 1332.31
  5005.8 1333.44  5027.0 1338.07  5034.1 1340.46  5048.2 1342.98  5055.3 1343.44
  5069.4 1346.51  5076.5 1348.86  5083.6 1350.35  5094.2 1353.81  5097.7 1353.81
#Mann=3,-1,0
  4816.4    0.12       0  4986.9    0.07       0  4990.9    0.12       0
Bank Sta=4986.9,4990.9
Exp/Cntr=0.3,0.1

Type RM Length L Ch R = 1,21542,445,445,445
BEGIN DESCRIPTION:
CEDAR HOLLOW CREEK 46.0
END DESCRIPTION:
XS GIS Cut Line= 3
      2852455.67     10287053.10      2852252.25     10286880.00
      2852005.65     10286703.08
#Sta/Elev= 30
  4732.9 1353.96  4775.1 1346.96  4811.4 1342.19  4818.0 1340.26  4832.3 1338.05
  4853.1 1332.80  4889.4 1327.35  4896.0 1325.50  4938.8 1321.14  4971.9 1316.18
  4972.2 1315.68  4975.9 1316.18  4988.2 1317.55  5008.7 1317.61  5023.5 1320.31
  5032.0 1319.60  5045.0 1321.33  5052.9 1320.76  5081.9 1324.16  5124.2 1325.74
  5153.6 1329.66  5168.1 1329.08  5174.5 1330.63  5180.7 1329.81  5231.0 1334.66
  5245.7 1337.19  5260.5 1342.52  5281.4 1346.83  5300.4 1353.03  5303.5 1353.03
#Mann=3,-1,0
  4732.9    0.12       0  4971.9    0.07       0  4975.9    0.12       0
Bank Sta=4971.9,4975.9
Exp/Cntr=0.3,0.1

Type RM Length L Ch R = 1,21097,471,471,471
BEGIN DESCRIPTION:
CEDAR HOLLOW CREEK 45.0
END DESCRIPTION:
XS GIS Cut Line= 3
      2852555.72     10286503.11      2852410.00     10286508.00
      2852205.65     10286303.08
#Sta/Elev= 30
  4854.2 1343.34  4874.2 1339.45  4924.3 1320.01  4954.3 1311.04  4974.3 1305.87
  4992.3 1304.07  4992.6 1303.57  4996.3 1304.07  4999.7 1306.37  5013.6 1307.24
  5020.7 1305.81  5027.7 1307.16  5041.9 1307.92  5091.4 1308.08  5112.6 1310.86
  5119.7 1310.66  5126.7 1313.40  5133.8 1313.98  5140.9 1318.18  5147.9 1319.75
  5155.0 1324.44  5162.1 1327.05  5169.1 1331.27  5190.4 1339.08  5211.6 1349.82
  5232.8 1357.77  5239.9 1362.86  5268.1 1377.88  5285.8 1384.94  5289.4 1384.94
#Mann=3,-1,0
  4854.2    0.12       0  4992.3    0.07       0  4996.3    0.12       0
Bank Sta=4992.3,4996.3
Exp/Cntr=0.3,0.1

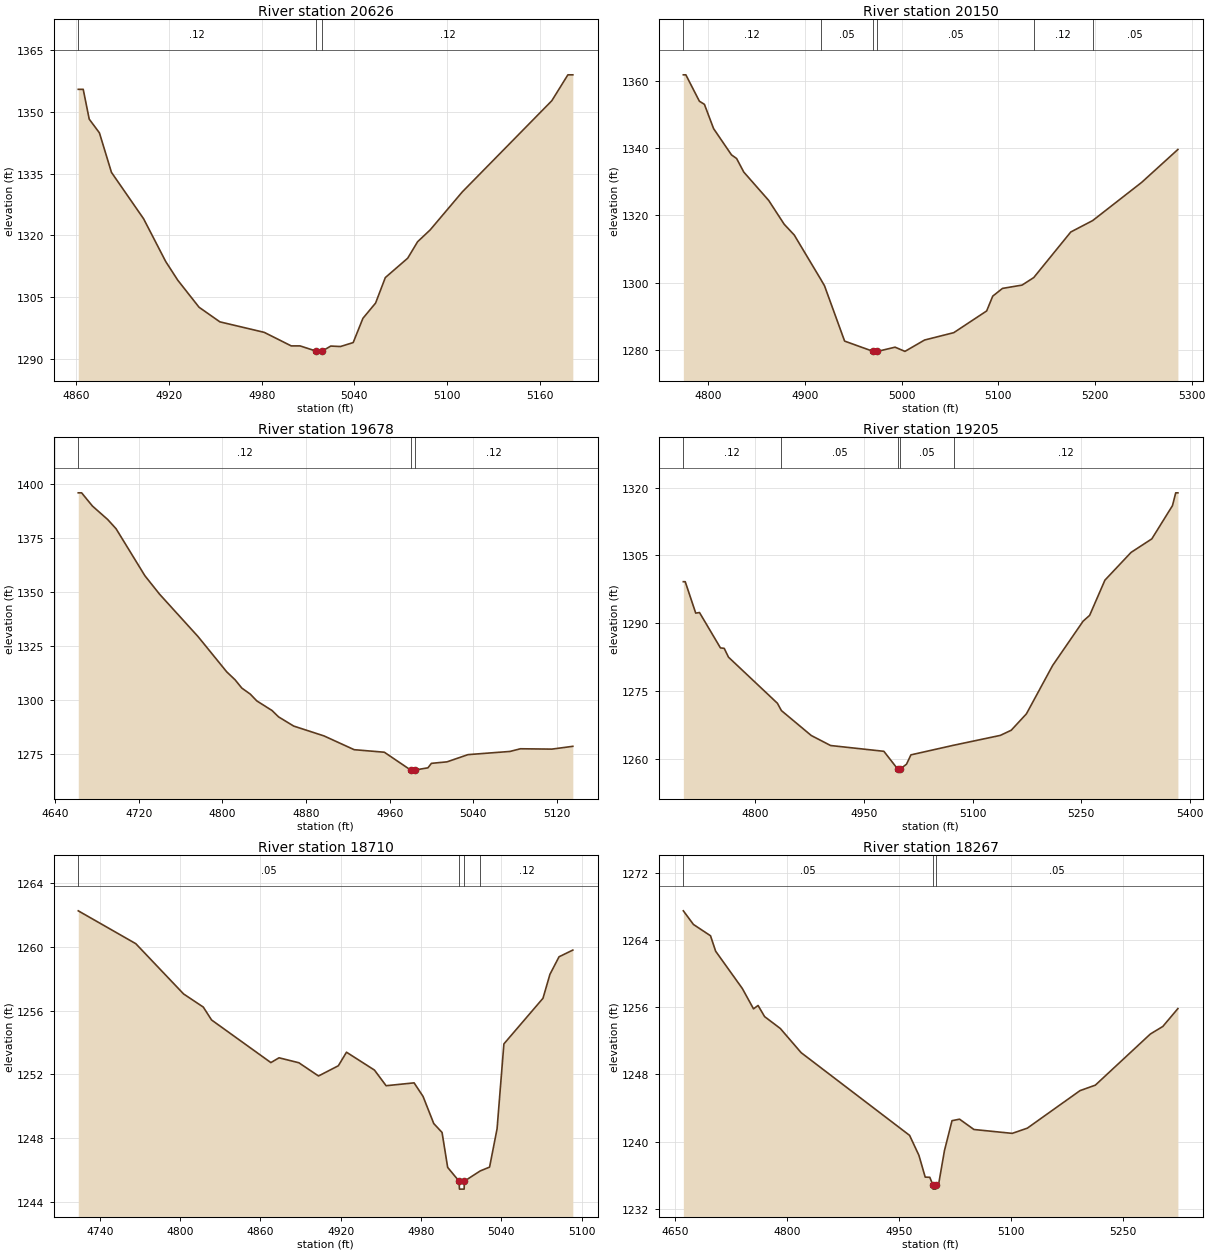
Type RM Length L Ch R = 1,20626,476,476,476
BEGIN DESCRIPTION:
CEDAR HOLLOW CREEK 44.0
END DESCRIPTION:
XS GIS Cut Line= 3
      2852705.67     10286203.10      2852599.25     10286114.00
      2852455.69     10286003.11
#Sta/Elev= 30
  4861.2 1355.39  4864.4 1355.39  4868.3 1348.17  4874.9 1344.85  4882.7 1335.28
  4903.5 1324.05  4917.8 1313.71  4925.6 1309.19  4939.4 1302.63  4952.9 1299.09
  4981.6 1296.55  4999.1 1293.27  5004.8 1293.27  5015.1 1292.02  5015.4 1291.52
  5018.9 1291.52  5019.1 1292.02  5024.7 1293.23  5031.0 1293.12  5039.2 1294.08
  5045.5 1299.95  5053.7 1303.64  5060.0 1309.81  5074.5 1314.51  5080.9 1318.49
  5089.0 1321.34  5109.8 1330.54  5167.8 1352.63  5178.2 1358.90  5181.4 1358.90
#Mann=3,-1,0
  4861.2    0.12       0  5015.1    0.07       0  5019.1    0.12       0
Bank Sta=5015.1,5019.1
Exp/Cntr=0.3,0.1

Type RM Length L Ch R = 1,20150,472,472,472
BEGIN DESCRIPTION:
CEDAR HOLLOW CREEK 43.0
END DESCRIPTION:
XS GIS Cut Line= 3
      2853105.66     10285803.10      2852889.25     10285739.00
      2852605.71     10285703.12
#Sta/Elev= 30
  4774.3 1361.83  4776.9 1361.83  4790.9 1353.98  4796.1 1353.05  4805.6 1345.82
  4824.1 1338.01  4829.4 1336.93  4836.8 1332.90  4862.6 1324.45  4878.6 1317.37
  4889.0 1314.17  4916.2 1301.10  4920.3 1299.06  4941.1 1282.60  4970.8 1279.52
  4971.0 1279.02  4974.8 1279.52  4993.3 1280.79  5003.5 1279.54  5023.8 1282.92
  5054.0 1285.11  5088.0 1291.57  5094.3 1295.98  5104.4 1298.28  5124.6 1299.26
  5136.7 1301.50  5175.0 1315.06  5197.7 1318.47  5248.3 1329.82  5285.8 1339.62
#Mann=6,-1,0
  4774.3    0.12       0  4916.2    0.05       0  4970.8    0.05       0
  4974.8    0.05       0  5136.7    0.12       0  5197.7    0.05       0
Bank Sta=4970.8,4974.8
Exp/Cntr=0.3,0.1

Type RM Length L Ch R = 1,19678,473,473,473
BEGIN DESCRIPTION:
CEDAR HOLLOW CREEK 42.0
END DESCRIPTION:
XS GIS Cut Line= 3
      2853305.67     10285503.10      2853040.50     10285294.00
      2852905.71     10285303.11
#Sta/Elev= 30
  4662.3 1395.93  4665.5 1395.93  4675.9 1389.77  4690.3 1383.61  4698.4 1379.30
  4726.0 1357.47  4740.0 1348.93  4776.9 1329.20  4804.2 1312.90  4812.2 1309.21
  4818.6 1305.39  4826.7 1302.58  4833.0 1299.41  4847.5 1294.97  4853.8 1292.00
  4868.3 1287.73  4897.2 1283.18  4926.1 1276.78  4954.9 1275.61  4980.1 1267.34
  4980.4 1266.84  4984.1 1267.34  4996.6 1268.38  4999.9 1270.45  5014.8 1271.14
  5034.9 1274.49  5075.0 1275.97  5085.0 1277.21  5115.1 1277.05  5135.1 1278.35
#Mann=3,-1,0
  4662.3    0.12       0  4980.1    0.07       0  4984.1    0.12       0
Bank Sta=4980.1,4984.1
Exp/Cntr=0.3,0.1

Type RM Length L Ch R = 1,19205,495,495,495
BEGIN DESCRIPTION:
CEDAR HOLLOW CREEK 41.0
END DESCRIPTION:
XS GIS Cut Line= 3
      2853455.69     10285253.12      2853375.00     10284965.00
      2853055.70     10284753.12
#Sta/Elev= 30
  4700.8 1299.18  4703.4 1299.18  4717.9 1292.22  4723.1 1292.35  4752.0 1284.52
  4757.2 1284.42  4763.1 1282.47  4830.6 1272.26  4836.1 1270.64  4877.3 1265.12
  4904.0 1262.90  4977.5 1261.62  4996.4 1257.73  4996.6 1257.23  5000.4 1257.73
  5008.8 1258.78  5014.8 1260.83  5074.3 1262.98  5138.1 1265.14  5153.2 1266.28
  5174.2 1269.92  5210.3 1280.61  5252.4 1290.44  5261.4 1291.72  5282.5 1299.52
  5318.6 1305.67  5347.2 1308.66  5375.7 1316.02  5380.2 1318.86  5383.2 1318.86
#Mann=5,-1,0
  4700.8    0.12       0  4836.1    0.05       0  4996.4    0.03       0
  5000.4    0.05       0  5074.3    0.12       0
Bank Sta=4996.4,5000.4
Exp/Cntr=0.3,0.1

Type RM Length L Ch R = 1,18710,443,443,443
BEGIN DESCRIPTION:
CEDAR HOLLOW CREEK 40.0
END DESCRIPTION:
XS GIS Cut Line= 3
      2853805.66     10284853.08      2853645.75     10284628.00
      2853555.72     10284603.12
#Sta/Elev= 30
  4723.9 1262.25  4766.9 1260.19  4802.6 1257.04  4817.3 1256.22  4823.5 1255.41
  4867.8 1252.74  4873.9 1253.04  4888.7 1252.73  4903.4 1251.90  4918.2 1252.54
  4924.3 1253.39  4945.2 1252.27  4953.9 1251.29  4974.8 1251.47  4981.5 1250.62
  4989.5 1248.92  4995.7 1248.36  4999.9 1246.17  5008.4 1245.31  5008.7 1244.81
  5012.2 1244.81  5012.4 1245.31  5024.2 1245.95  5031.2 1246.19  5036.8 1248.59
  5041.9 1253.91  5071.1 1256.77  5076.3 1258.27  5083.1 1259.37  5093.4 1259.79
#Mann=4,-1,0
  4723.9    0.05       0  5008.4    0.05       0  5012.4    0.05       0
  5024.2    0.12       0
Bank Sta=5008.4,5012.4
Exp/Cntr=0.3,0.1

Type RM Length L Ch R = 1,18267,474,474,474
BEGIN DESCRIPTION:
CEDAR HOLLOW CREEK 39.0
END DESCRIPTION:
XS GIS Cut Line= 3
      2854205.69     10284503.11      2853926.50     10284311.00
      2853605.65     10284353.12
#Sta/Elev= 30
  4661.1 1267.48  4674.6 1265.86  4697.5 1264.51  4704.4 1262.67  4740.2 1258.22
  4755.1 1255.81  4761.2 1256.21  4770.0 1254.88  4791.0 1253.47  4818.9 1250.59
  4964.2 1240.74  4976.7 1238.36  4985.1 1235.77  4991.2 1235.75  4995.5 1234.84
  4995.7 1234.34  4999.2 1234.34  4999.5 1234.84  5002.9 1234.84  5010.9 1238.93
  5021.0 1242.49  5031.1 1242.67  5050.4 1241.44  5101.7 1240.98  5121.9 1241.60
  5192.5 1246.07  5213.0 1246.72  5286.7 1252.81  5303.4 1253.71  5323.6 1255.84
#Mann=3,-1,0
  4661.1    0.05       0  4995.5    0.03       0  4999.5    0.05       0
Bank Sta=4995.5,4999.5
Exp/Cntr=0.3,0.1

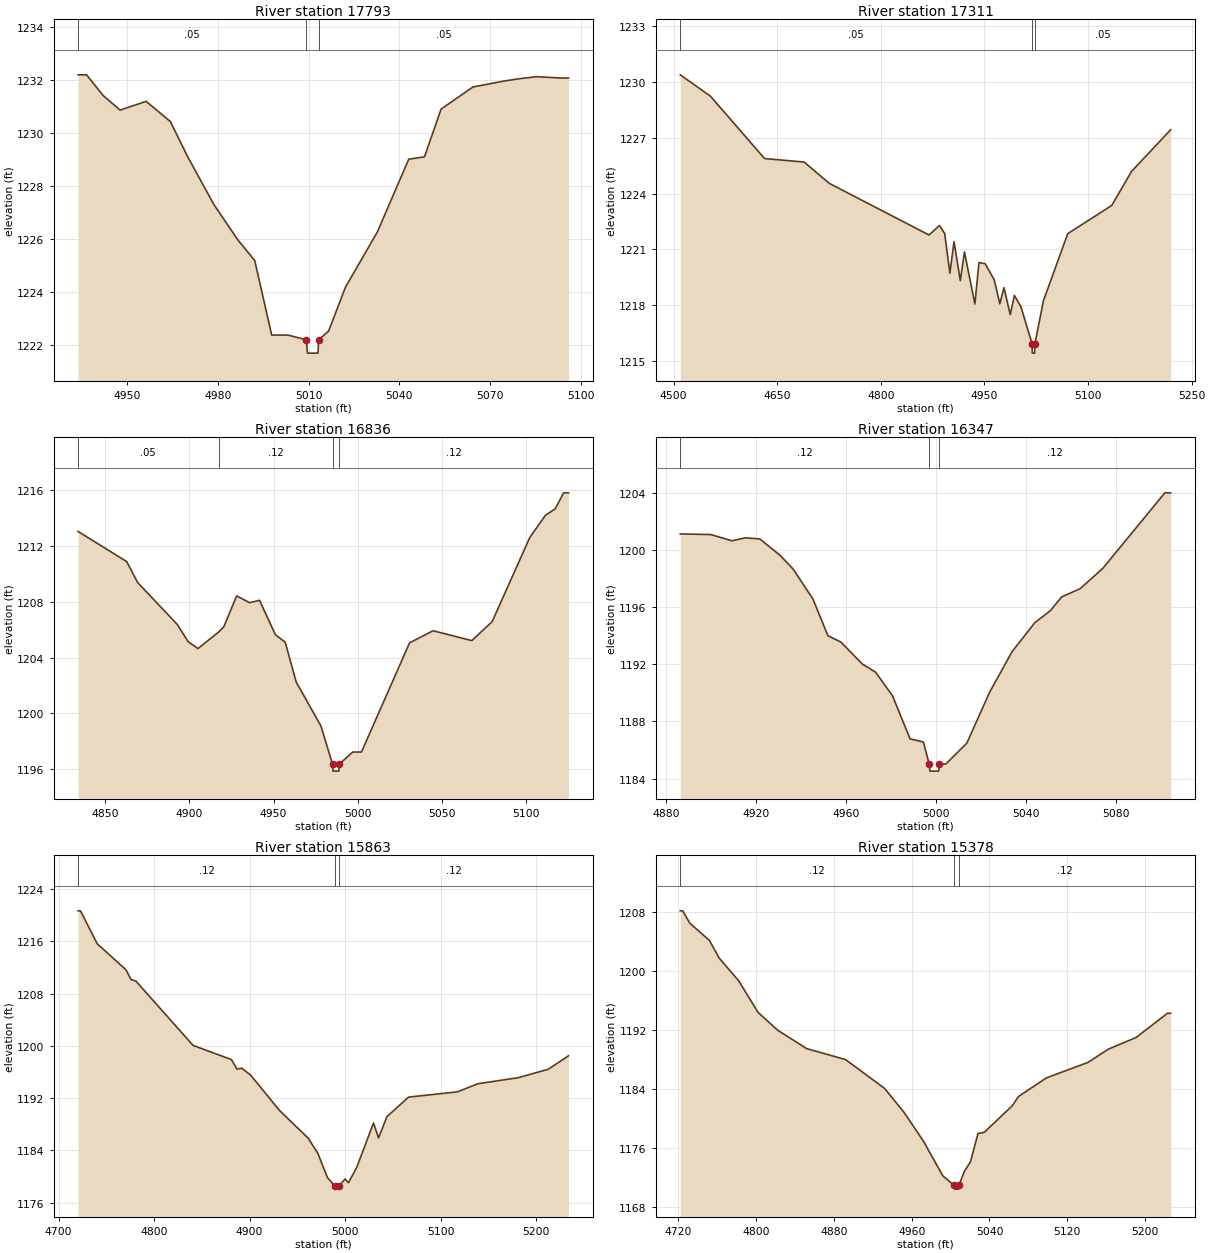
Type RM Length L Ch R = 1,17793,482,482,482
BEGIN DESCRIPTION:
CEDAR HOLLOW CREEK 38.0
END DESCRIPTION:
XS GIS Cut Line= 3
      2854155.70     10283903.12      2854096.75     10283873.00
      2854005.70     10283903.11
#Sta/Elev= 29
  4933.8 1232.19  4936.6 1232.19  4942.1 1231.41  4947.7 1230.86  4956.3 1231.19
  4964.3 1230.43  4970.0 1229.11  4978.7 1227.30  4986.6 1225.97  4992.2 1225.19
  4997.8 1222.38  5000.0 1222.38  5003.2 1222.38  5009.3 1222.20  5009.6 1221.70
  5013.1 1221.70  5013.3 1222.20  5016.6 1222.53  5022.2 1224.19  5032.7 1226.26
  5043.1 1229.01  5048.3 1229.10  5053.8 1230.90  5064.3 1231.73  5074.8 1231.96
  5080.1 1232.05  5085.4 1232.12  5093.3 1232.07  5095.9 1232.07
#Mann=3,-1,0
  4933.8    0.05       0  5009.3    0.05       0  5013.3    0.05       0
Bank Sta=5009.3,5013.3
Exp/Cntr=0.3,0.1

Type RM Length L Ch R = 1,17311,475,475,475
BEGIN DESCRIPTION:
CEDAR HOLLOW CREEK 37.0
END DESCRIPTION:
XS GIS Cut Line= 3
      2854405.71     10283703.13      2853995.75     10283434.00
      2853855.67     10283603.12
#Sta/Elev= 30
  4509.6 1230.38  4553.3 1229.23  4631.6 1225.88  4689.1 1225.69  4725.1 1224.55
  4869.7 1221.77  4884.8 1222.28  4892.4 1221.85  4899.9 1219.72  4905.9 1221.41
  4915.0 1219.32  4921.0 1220.86  4936.1 1218.06  4942.0 1220.29  4951.2 1220.22
  4964.2 1219.35  4972.2 1218.07  4978.2 1218.94  4987.3 1217.49  4993.3 1218.52
  5002.7 1217.92  5019.0 1215.92  5019.2 1215.42  5022.7 1215.42  5023.0 1215.92
  5035.3 1218.23  5070.5 1221.84  5134.3 1223.36  5162.9 1225.19  5219.6 1227.43
#Mann=3,-1,0
  4509.6    0.05       0  5019.0    0.03       0  5023.0    0.05       0
Bank Sta=5019,5023
Exp/Cntr=0.3,0.1

Type RM Length L Ch R = 1,16836,489,489,489
BEGIN DESCRIPTION:
CEDAR HOLLOW CREEK 36.0
END DESCRIPTION:
XS GIS Cut Line= 3
      2854155.67     10283103.11      2854014.75     10283015.00
      2853905.69     10282953.11
#Sta/Elev= 30
  4833.8 1213.05  4862.7 1210.89  4869.2 1209.39  4892.8 1206.38  4899.2 1205.15
  4905.1 1204.65  4917.3 1205.83  4920.5 1206.22  4928.1 1208.43  4935.8 1207.94
  4941.7 1208.11  4951.1 1205.65  4957.0 1205.10  4963.5 1202.25  4978.2 1199.10
  4985.1 1196.36  4985.4 1195.86  4988.9 1195.86  4989.1 1196.36  4997.1 1197.23
  5002.3 1197.23  5030.9 1205.06  5044.9 1205.93  5067.9 1205.22  5080.0 1206.58
  5102.4 1212.62  5111.7 1214.21  5117.5 1214.67  5122.5 1215.82  5125.4 1215.82
#Mann=4,-1,0
  4833.8    0.05       0  4917.3    0.12       0  4985.1    0.07       0
  4989.1    0.12       0
Bank Sta=4985.1,4989.1
Exp/Cntr=0.3,0.1

Type RM Length L Ch R = 1,16347,484,484,484
BEGIN DESCRIPTION:
CEDAR HOLLOW CREEK 35.0
END DESCRIPTION:
XS GIS Cut Line= 3
      2854205.65     10282603.09      2854109.25     10282543.00
      2854005.64     10282553.12
#Sta/Elev= 30
  4886.4 1201.13  4899.9 1201.09  4909.4 1200.65  4915.3 1200.86  4921.7 1200.78
  4930.6 1199.65  4936.5 1198.67  4945.3 1196.57  4951.9 1194.01  4957.7 1193.56
  4967.2 1192.02  4973.1 1191.45  4980.6 1189.80  4988.4 1186.78  4994.3 1186.56
  4996.9 1185.02  4997.2 1184.52  5001.1 1184.52  5001.4 1185.02  5004.3 1185.02
  5013.6 1186.48  5023.7 1190.04  5033.7 1192.89  5043.8 1194.92  5050.7 1195.76
  5055.7 1196.72  5063.9 1197.30  5073.9 1198.71  5101.5 1204.01  5104.1 1204.01
#Mann=3,-1,0
  4886.4    0.12       0  4996.9    0.07       0  5001.4    0.12       0
Bank Sta=4996.9,5001.4
Exp/Cntr=0.3,0.1

Type RM Length L Ch R = 1,15863,485,485,485
BEGIN DESCRIPTION:
CEDAR HOLLOW CREEK 34.0
END DESCRIPTION:
XS GIS Cut Line= 3
      2854505.72     10282103.11      2854227.25     10282078.00
      2854005.64     10282153.13
#Sta/Elev= 30
  4720.4 1220.67  4722.9 1220.67  4740.5 1215.62  4770.6 1211.65  4775.9 1210.14
  4780.9 1209.93  4840.9 1200.07  4881.1 1197.90  4886.8 1196.44  4891.8 1196.59
  4901.2 1195.52  4931.3 1190.13  4961.4 1185.88  4971.5 1183.56  4981.5 1179.86
  4989.2 1178.58  4989.5 1178.08  4993.9 1178.58  5000.0 1179.63  5003.6 1179.06
  5012.2 1181.40  5029.8 1188.20  5035.1 1185.92  5043.9 1189.18  5066.5 1192.16
  5117.8 1192.97  5138.9 1194.20  5181.2 1195.13  5212.8 1196.42  5234.0 1198.49
#Mann=3,-1,0
  4720.4    0.12       0  4989.2    0.07       0  4993.9    0.12       0
Bank Sta=4989.2,4993.9
Exp/Cntr=0.3,0.1

Type RM Length L Ch R = 1,15378,467,467,467
BEGIN DESCRIPTION:
CEDAR HOLLOW CREEK 33.0
END DESCRIPTION:
XS GIS Cut Line= 3
      2854355.63     10281653.11      2854077.75     10281656.00
      2853905.67     10281803.12
#Sta/Elev= 30
  4722.1 1208.13  4724.6 1208.13  4732.1 1206.43  4752.1 1204.12  4762.1 1201.73
  4782.1 1198.66  4802.1 1194.37  4822.1 1191.97  4852.1 1189.46  4892.1 1187.97
  4932.1 1184.08  4952.1 1180.84  4972.1 1176.93  4992.1 1172.21  5003.9 1170.92
  5004.3 1170.42  5008.3 1170.42  5008.6 1170.92  5014.0 1172.77  5020.5 1174.13
  5028.2 1177.95  5034.8 1178.13  5063.4 1181.71  5069.9 1182.97  5098.5 1185.49
  5141.3 1187.59  5162.2 1189.38  5190.7 1190.96  5223.1 1194.25  5226.4 1194.25
#Mann=3,-1,0
  4722.1    0.12       0  5003.9    0.07       0  5008.6    0.12       0
Bank Sta=5003.9,5008.6
Exp/Cntr=0.3,0.1

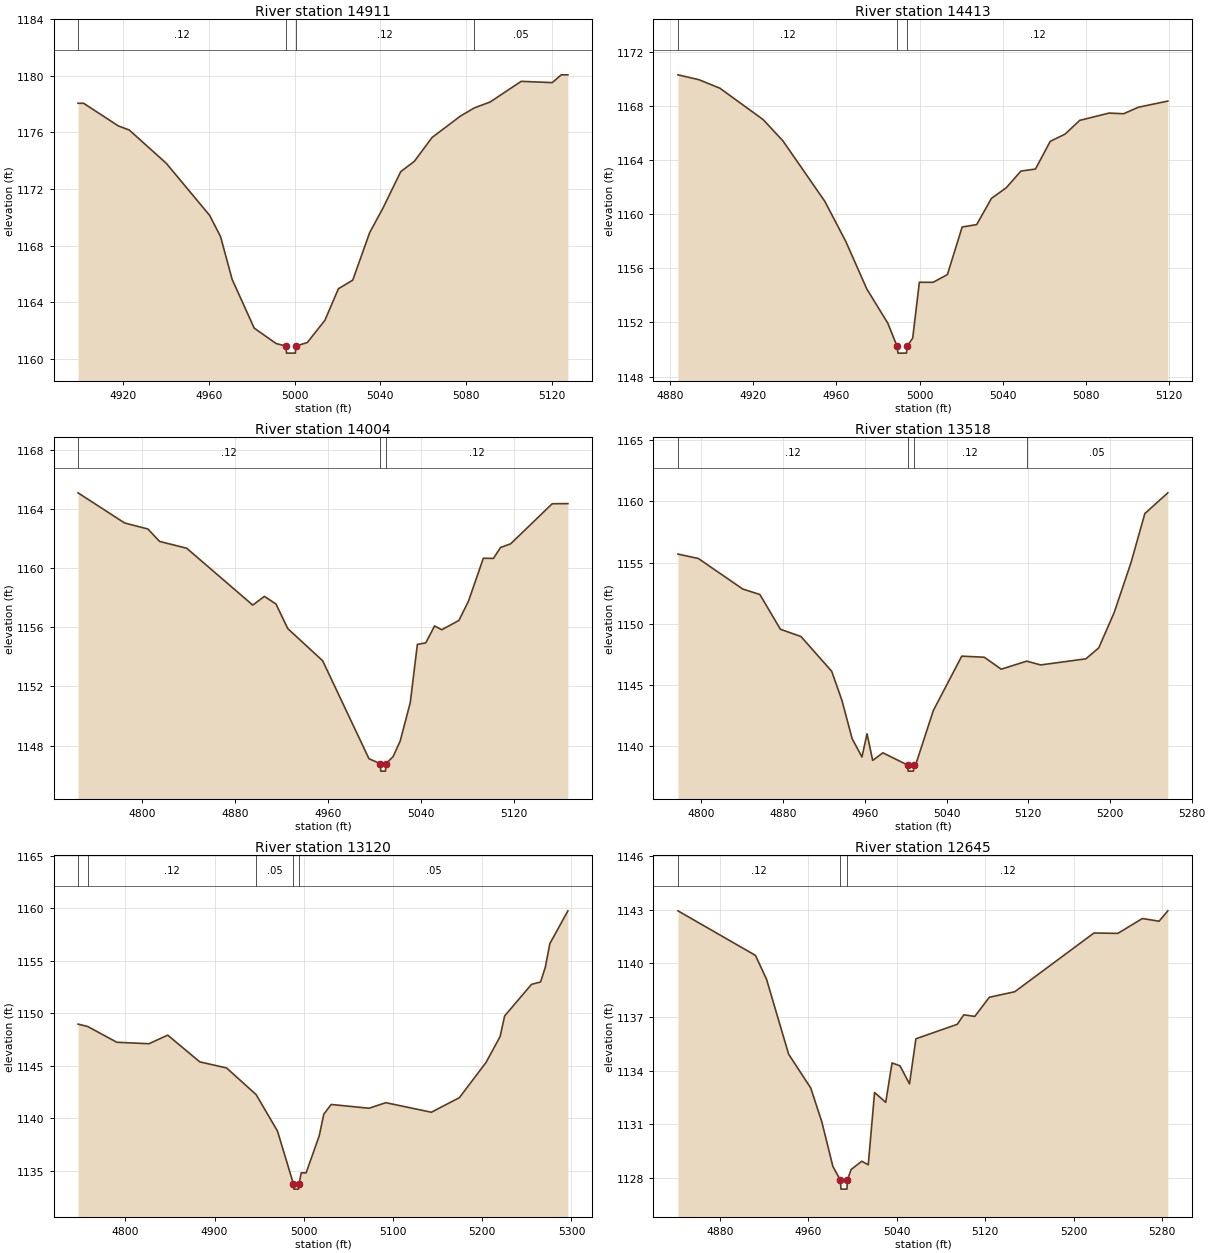
Type RM Length L Ch R = 1,14911,498,498,498
BEGIN DESCRIPTION:
CEDAR HOLLOW CREEK 32.0
END DESCRIPTION:
XS GIS Cut Line= 3
      2853905.72     10281253.10      2853807.25     10281276.00
      2853705.70     10281353.10
#Sta/Elev= 30
  4898.9 1178.06  4901.5 1178.06  4917.7 1176.46  4922.8 1176.17  4940.0 1173.83
  4960.3 1170.14  4965.4 1168.64  4970.8 1165.62  4981.1 1162.17  4991.3 1161.08
  4995.9 1160.90  4996.2 1160.40  5000.3 1160.40  5000.6 1160.90  5005.9 1161.15
  5014.1 1162.72  5020.4 1164.95  5027.1 1165.56  5035.0 1168.92  5041.2 1170.65
  5049.5 1173.23  5055.8 1173.95  5064.1 1175.64  5077.3 1177.15  5083.8 1177.73
  5091.2 1178.15  5105.7 1179.61  5120.2 1179.52  5124.4 1180.07  5127.5 1180.07
#Mann=4,-1,0
  4898.9    0.12       0  4995.9    0.07       0  5000.6    0.12       0
  5083.8    0.05       0
Bank Sta=4995.9,5000.6
Exp/Cntr=0.3,0.1

Type RM Length L Ch R = 1,14413,409,409,409
BEGIN DESCRIPTION:
CEDAR HOLLOW CREEK 31.0
END DESCRIPTION:
XS GIS Cut Line= 3
      2853755.71     10280803.11      2853640.50     10280819.00
      2853555.65     10280903.15
#Sta/Elev= 30
  4883.7 1170.32  4893.8 1169.96  4903.9 1169.33  4924.7 1167.01  4934.2 1165.44
  4954.4 1160.96  4964.5 1157.99  4974.6 1154.48  4984.7 1151.95  4989.2 1150.23
  4989.6 1149.73  4993.7 1149.73  4994.0 1150.23  4996.7 1150.84  4999.9 1154.97
  5006.5 1154.97  5013.4 1155.54  5020.5 1159.06  5027.5 1159.24  5034.6 1161.18
  5041.7 1161.96  5048.8 1163.20  5055.8 1163.35  5062.9 1165.40  5070.0 1165.93
  5077.1 1166.95  5091.2 1167.49  5098.2 1167.44  5105.3 1167.92  5119.5 1168.38
#Mann=3,-1,0
  4883.7    0.12       0  4989.2    0.07       0  4994.0    0.12       0
Bank Sta=4989.2,4994
Exp/Cntr=0.3,0.1

Type RM Length L Ch R = 1,14004,486,486,486
BEGIN DESCRIPTION:
CEDAR HOLLOW CREEK 30.0
END DESCRIPTION:
XS GIS Cut Line= 3
      2853655.67     10280503.11      2853401.25     10280517.00
      2853305.69     10280653.10
#Sta/Elev= 30
  4745.2 1165.11  4785.2 1163.07  4805.3 1162.66  4815.3 1161.82  4838.6 1161.36
  4895.4 1157.51  4905.4 1158.10  4915.4 1157.58  4925.5 1155.92  4955.5 1153.74
  4995.3 1147.11  5005.1 1146.77  5005.4 1146.27  5009.5 1146.27  5009.9 1146.77
  5016.0 1147.25  5022.1 1148.30  5030.8 1150.91  5036.9 1154.85  5044.1 1154.95
  5051.7 1156.10  5057.8 1155.84  5072.6 1156.47  5080.8 1157.77  5093.6 1160.68
  5102.3 1160.67  5108.4 1161.41  5117.1 1161.66  5152.8 1164.37  5166.3 1164.38
#Mann=3,-1,0
  4745.2    0.12       0  5005.1    0.07       0  5009.9    0.12       0
Bank Sta=5005.1,5009.9
Exp/Cntr=0.3,0.1

Type RM Length L Ch R = 1,13518,398,398,398
BEGIN DESCRIPTION:
CEDAR HOLLOW CREEK 29.0
END DESCRIPTION:
XS GIS Cut Line= 3
      2853355.66     10280153.11      2853133.50     10280135.00
      2852905.70     10280253.11
#Sta/Elev= 30
  4777.1 1155.69  4797.1 1155.33  4840.5 1152.83  4857.3 1152.38  4877.4 1149.53
  4897.5 1148.94  4927.6 1146.09  4937.6 1143.71  4947.6 1140.57  4957.2 1139.07
  4962.2 1140.97  4967.7 1138.79  4977.7 1139.41  5001.9 1138.41  5002.4 1137.91
  5007.6 1137.91  5008.1 1138.41  5010.6 1138.64  5027.1 1142.88  5054.9 1147.33
  5077.0 1147.24  5093.5 1146.26  5118.5 1146.92  5132.1 1146.61  5176.4 1147.11
  5189.0 1148.01  5204.1 1150.90  5220.6 1155.00  5234.1 1159.01  5256.6 1160.71
#Mann=4,-1,0
  4777.1    0.12       0  5001.9    0.07       0  5008.1    0.12       0
  5118.5    0.05       0
Bank Sta=5001.9,5008.1
Exp/Cntr=0.3,0.1

Type RM Length L Ch R = 1,13120,475,475,475
BEGIN DESCRIPTION:
CEDAR HOLLOW CREEK 28.0
END DESCRIPTION:
XS GIS Cut Line= 3
      2853005.71     10279653.07      2852864.50     10279863.00
      2852805.69     10280153.10
#Sta/Elev= 30
  4747.0 1148.96  4757.9 1148.73  4790.5 1147.23  4826.5 1147.09  4847.5 1147.91
  4883.5 1145.36  4913.5 1144.78  4946.6 1142.24  4970.5 1138.77  4988.4 1133.73
  4988.9 1133.23  4994.2 1133.23  4994.7 1133.73  4997.1 1134.78  5002.6 1134.78
  5017.3 1138.31  5022.4 1140.37  5030.7 1141.30  5073.1 1140.94  5091.9 1141.47
  5143.0 1140.56  5174.4 1141.95  5204.2 1145.30  5220.0 1147.77  5225.1 1149.74
  5255.2 1152.75  5265.4 1152.98  5270.7 1154.39  5275.8 1156.64  5296.0 1159.76
#Mann=5,-1,0
  4747.0    0.05       0  4757.9    0.12       0  4946.6    0.05       0
  4988.4    0.05       0  4994.7    0.05       0
Bank Sta=4988.4,4994.7
Exp/Cntr=0.3,0.1

Type RM Length L Ch R = 1,12645,435,435,435
BEGIN DESCRIPTION:
CEDAR HOLLOW CREEK 27.0
END DESCRIPTION:
XS GIS Cut Line= 3
      2852855.72     10279453.11      2852697.75     10279456.00
      2852555.70     10279703.08
#Sta/Elev= 30
  4842.0 1142.93  4912.1 1140.44  4922.1 1139.11  4942.1 1134.92  4962.1 1133.03
  4972.1 1131.14  4982.1 1128.65  4988.9 1127.88  4989.4 1127.38  4994.8 1127.38
  4995.3 1127.88  4998.5 1128.47  5008.2 1128.94  5014.1 1128.74  5019.8 1132.78
  5029.9 1132.23  5035.6 1134.43  5042.8 1134.27  5051.4 1133.26  5057.2 1135.78
  5094.6 1136.59  5100.5 1137.12  5110.4 1137.03  5123.6 1138.10  5146.6 1138.41
  5218.2 1141.69  5239.8 1141.67  5262.0 1142.50  5277.1 1142.35  5285.0 1142.93
#Mann=3,-1,0
  4842.0    0.12       0  4988.9    0.07       0  4995.3    0.12       0
Bank Sta=4988.9,4995.3
Exp/Cntr=0.3,0.1

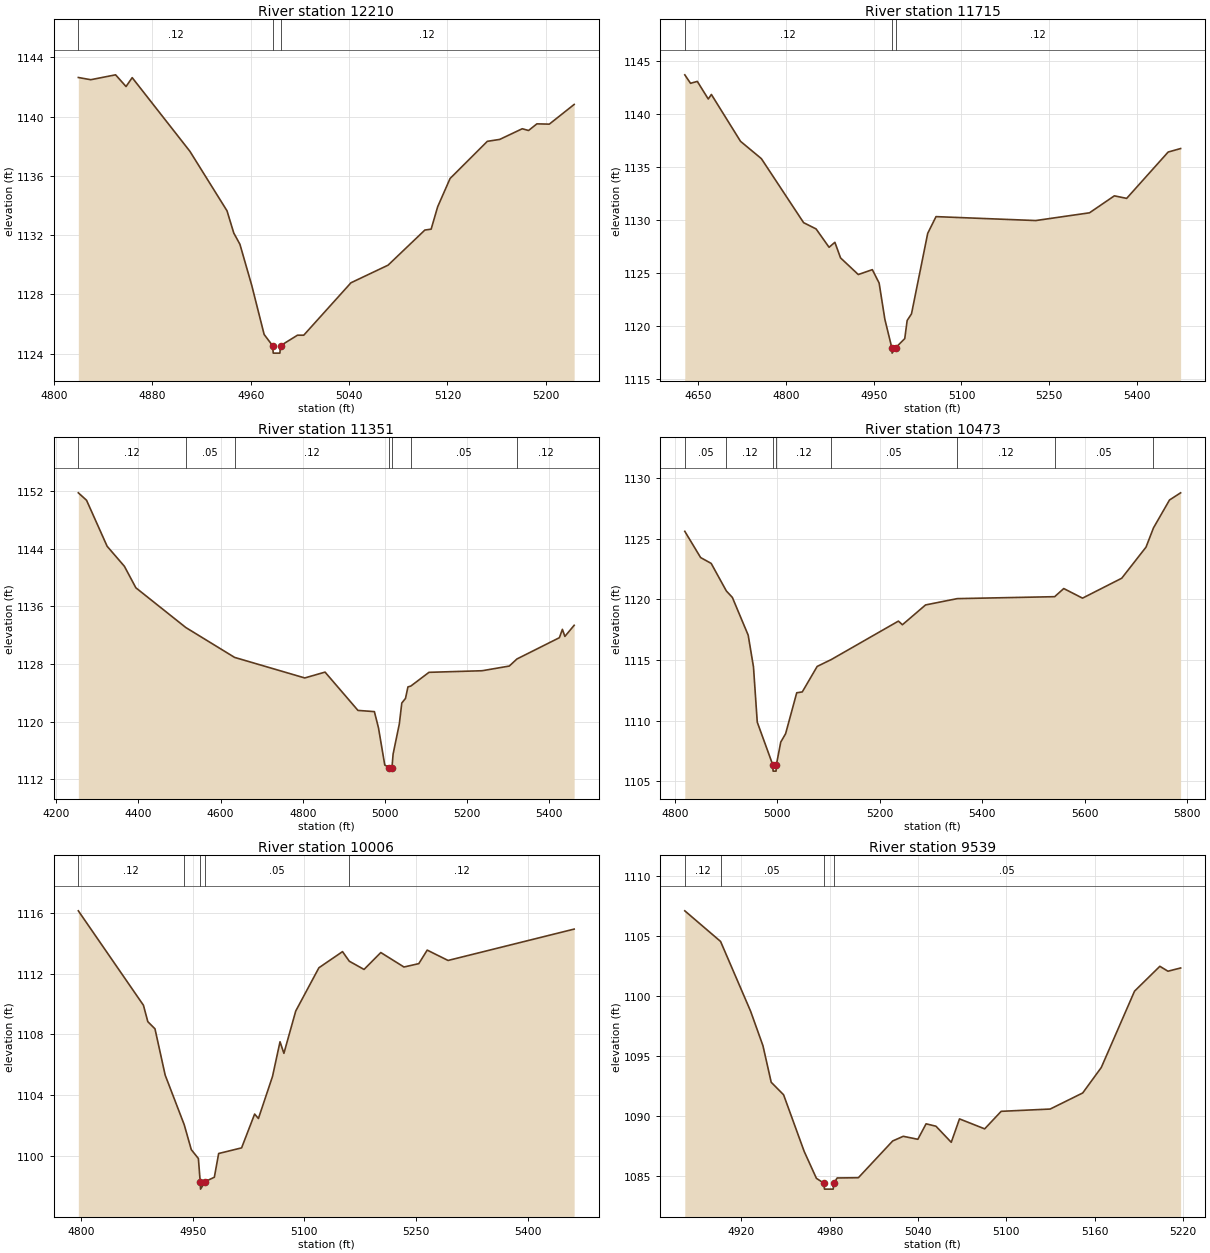
Type RM Length L Ch R = 1,12210,495,495,495
BEGIN DESCRIPTION:
CEDAR HOLLOW CREEK 26.0
END DESCRIPTION:
XS GIS Cut Line= 3
      2852405.68     10279203.07      2852427.00     10279382.00
      2852455.69     10279603.15
#Sta/Elev= 30
  4819.8 1142.64  4829.9 1142.49  4850.1 1142.82  4858.6 1142.03  4863.6 1142.63
  4910.5 1137.66  4940.7 1133.64  4946.2 1132.14  4951.2 1131.38  4960.8 1128.61
  4970.9 1125.29  4977.8 1124.53  4978.3 1124.03  4983.7 1124.03  4984.2 1124.53
  4998.0 1125.24  5003.1 1125.24  5041.5 1128.78  5071.7 1129.97  5101.6 1132.34
  5106.7 1132.40  5112.0 1133.91  5122.1 1135.82  5152.4 1138.33  5162.5 1138.46
  5180.8 1139.18  5185.9 1139.06  5192.7 1139.51  5202.8 1139.49  5223.0 1140.82
#Mann=3,-1,0
  4819.8    0.12       0  4977.8    0.07       0  4984.2    0.12       0
Bank Sta=4977.8,4984.2
Exp/Cntr=0.3,0.1

Type RM Length L Ch R = 1,11715,364,364,364
BEGIN DESCRIPTION:
CEDAR HOLLOW CREEK 25.0
END DESCRIPTION:
XS GIS Cut Line= 3
      2852355.71     10279103.10      2852006.75     10279234.00
      2851655.70     10279553.09
#Sta/Elev= 30
  4627.3 1143.66  4637.1 1142.86  4648.7 1143.04  4667.4 1141.38  4672.7 1141.81
  4722.5 1137.39  4758.1 1135.76  4830.3 1129.72  4851.6 1129.13  4873.8 1127.40
  4883.7 1127.87  4893.4 1126.40  4923.7 1124.83  4947.7 1125.29  4959.3 1124.03
  4969.1 1120.61  4981.0 1117.92  4981.5 1117.42  4987.4 1117.92  5003.1 1118.79
  5007.2 1120.50  5014.6 1121.12  5042.3 1128.71  5056.5 1130.29  5226.8 1129.92
  5318.7 1130.65  5361.2 1132.25  5382.2 1132.01  5453.1 1136.38  5474.4 1136.71
#Mann=3,-1,0
  4627.3    0.12       0  4981.0    0.07       0  4987.4    0.12       0
Bank Sta=4981,4987.4
Exp/Cntr=0.3,0.1

Type RM Length L Ch R = 1,11351,878,878,878
BEGIN DESCRIPTION:
CEDAR HOLLOW CREEK 24.0
END DESCRIPTION:
XS GIS Cut Line= 3
      2852505.67     10279003.11      2851760.25     10278969.00
      2851505.69     10279353.10
#Sta/Elev= 30
  4253.8 1151.73  4273.8 1150.70  4323.9 1144.32  4366.0 1141.54  4393.9 1138.56
  4515.5 1133.05  4634.2 1128.91  4805.0 1126.06  4854.4 1126.87  4934.5 1121.56
  4974.5 1121.39  4984.5 1119.13  4999.8 1113.98  5010.9 1113.64  5011.4 1113.14
  5017.3 1113.64  5020.1 1115.52  5035.2 1119.68  5041.2 1122.58  5050.2 1123.22
  5056.2 1124.82  5063.1 1124.93  5107.4 1126.84  5236.7 1127.06  5302.9 1127.71
  5321.5 1128.69  5424.8 1131.64  5432.2 1132.80  5438.2 1131.82  5460.8 1133.36
#Mann=7,-1,0
  4253.8    0.12       0  4515.5    0.05       0  4634.2    0.12       0
  5010.9    0.07       0  5017.3    0.12       0  5063.1    0.05       0
  5321.5    0.12       0
Bank Sta=5010.9,5017.3
Exp/Cntr=0.3,0.1

Type RM Length L Ch R = 1,10473,467,467,467
BEGIN DESCRIPTION:
CEDAR HOLLOW CREEK 23.0
END DESCRIPTION:
XS GIS Cut Line= 3
      2851755.68     10278153.13      2851711.75     10278328.00
      2851405.67     10279053.15
#Sta/Elev= 30
  4819.7 1125.59  4850.6 1123.43  4871.2 1122.95  4900.8 1120.68  4912.5 1120.15
  4943.4 1117.04  4953.7 1114.43  4961.1 1109.88  4991.5 1106.35  4992.0 1105.85
  4997.8 1105.85  4998.3 1106.35  5006.9 1108.24  5016.4 1108.93  5038.1 1112.30
  5048.9 1112.37  5078.0 1114.47  5105.7 1115.04  5236.5 1118.20  5244.3 1117.90
  5289.4 1119.53  5351.2 1120.05  5541.3 1120.21  5559.1 1120.88  5595.7 1120.09
  5672.2 1121.73  5719.6 1124.29  5734.1 1125.87  5765.4 1128.17  5787.1 1128.76
#Mann=8,-1,0
  4819.7    0.05       0  4900.8    0.12       0  4991.5    0.07       0
  4998.3    0.12       0  5105.7    0.05       0  5351.2    0.12       0
  5541.3    0.05       0  5734.1    0.12       0
Bank Sta=4991.5,4998.3
Exp/Cntr=0.3,0.1

Type RM Length L Ch R = 1,10006,467,467,467
BEGIN DESCRIPTION:
CEDAR HOLLOW CREEK 22.0
END DESCRIPTION:
XS GIS Cut Line= 3
      2851455.65     10278053.13      2851281.25     10278158.00
      2851405.69     10278603.13
#Sta/Elev= 30
  4796.5 1116.12  4883.9 1109.92  4889.8 1108.84  4899.4 1108.37  4913.1 1105.33
  4938.6 1102.08  4948.2 1100.43  4957.7 1099.85  4960.1 1098.34  4960.6 1097.84
  4966.9 1098.34  4979.1 1098.62  4984.9 1100.18  5015.7 1100.55  5033.2 1102.77
  5038.3 1102.48  5057.2 1105.24  5067.3 1107.52  5072.5 1106.76  5088.4 1109.54
  5119.5 1112.38  5151.2 1113.44  5160.3 1112.81  5180.1 1112.27  5202.6 1113.38
  5233.7 1112.43  5253.6 1112.65  5264.9 1113.54  5292.9 1112.86  5462.2 1114.92
#Mann=5,-1,0
  4796.5    0.12       0  4938.6    0.05       0  4960.1    0.05       0
  4966.9    0.05       0  5160.3    0.12       0
Bank Sta=4960.1,4966.9
Exp/Cntr=0.3,0.1

Type RM Length L Ch R = 1,9539,457,457,457
BEGIN DESCRIPTION:
CEDAR HOLLOW CREEK 21.0
END DESCRIPTION:
XS GIS Cut Line= 3
      2851005.68     10277853.11      2850899.75     10277906.00
      2850805.69     10278103.11
#Sta/Elev= 30
  4881.6 1107.12  4905.9 1104.57  4926.3 1098.76  4934.7 1095.88  4940.3 1092.84
  4948.7 1091.80  4962.7 1087.08  4971.0 1084.84  4976.0 1084.44  4976.5 1083.94
  4982.4 1083.94  4982.9 1084.44  4985.1 1084.87  4999.5 1084.89  5022.8 1087.95
  5030.0 1088.34  5039.9 1088.09  5045.5 1089.38  5052.2 1089.18  5062.6 1087.84
  5068.2 1089.79  5085.3 1088.96  5096.5 1090.42  5129.8 1090.61  5151.9 1091.95
  5164.5 1094.07  5187.1 1100.43  5204.3 1102.50  5209.8 1102.09  5218.4 1102.36
#Mann=4,-1,0
  4881.6    0.12       0  4905.9    0.05       0  4976.0    0.05       0
  4982.9    0.05       0
Bank Sta=4976,4982.9
Exp/Cntr=0.3,0.1