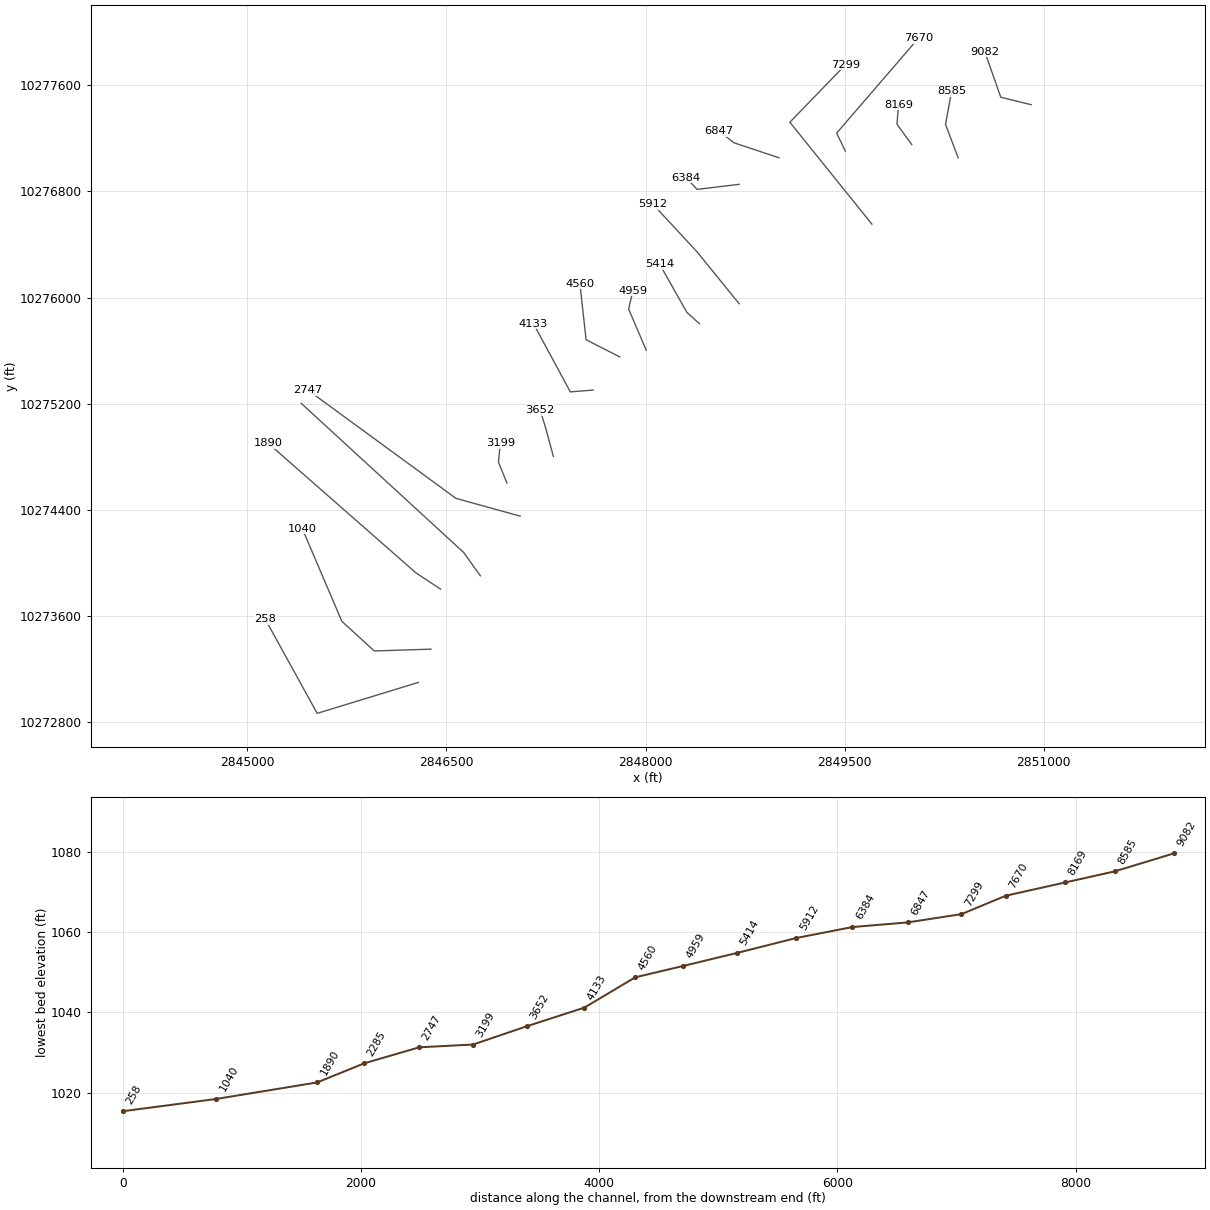
HEC-RAS study CEDAR HOLLOW CREEK.prj: CEDAR HOLLOW CREEK Base Level Engineering

--- CEDAR HOLLOW CREEK.g01 (geometry) --- (continued)

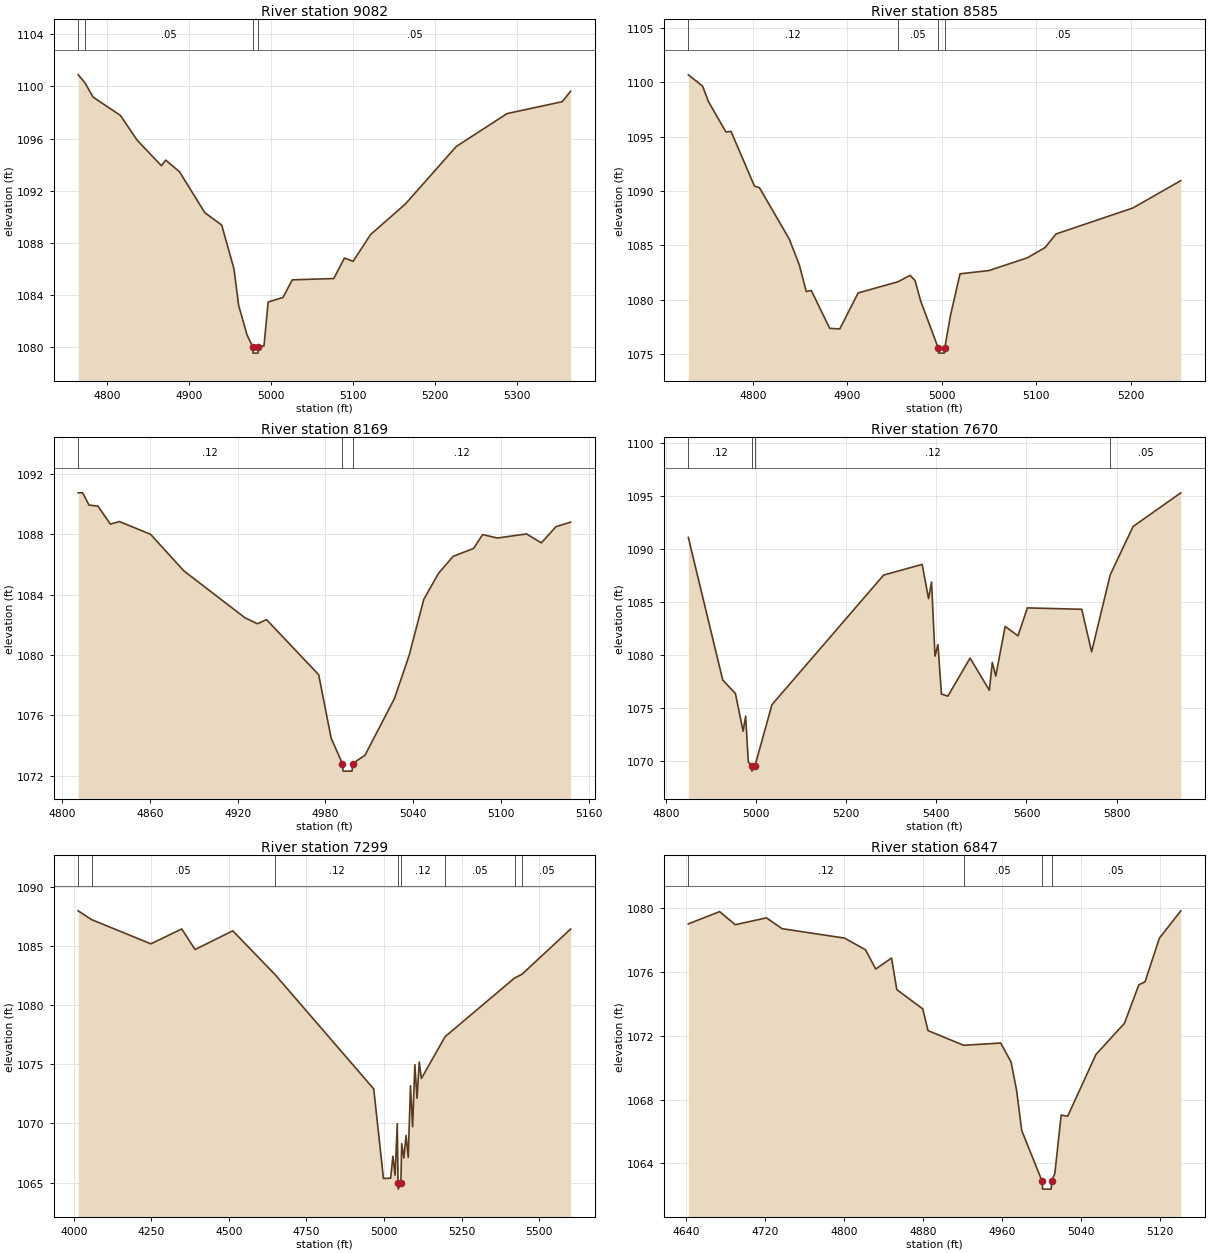
Type RM Length L Ch R = 1,9082,497,497,497
BEGIN DESCRIPTION:
CEDAR HOLLOW CREEK 20.0
END DESCRIPTION:
XS GIS Cut Line= 3
      2850905.67     10277453.12      2850677.00     10277509.00
      2850555.67     10277853.14
#Sta/Elev= 30
  4764.6 1100.89  4772.7 1100.30  4782.8 1099.18  4816.1 1097.78  4836.6 1095.87
  4866.1 1093.92  4871.3 1094.35  4888.1 1093.46  4919.0 1090.32  4939.6 1089.37
  4954.6 1085.99  4960.2 1083.22  4970.5 1080.94  4977.3 1080.05  4977.8 1079.55
  4983.8 1079.55  4984.3 1080.05  4991.1 1080.10  4996.2 1083.47  5014.3 1083.82
  5025.6 1085.17  5076.2 1085.27  5089.2 1086.84  5099.8 1086.59  5121.0 1088.64
  5163.4 1090.98  5225.6 1095.40  5287.5 1097.92  5354.7 1098.83  5364.9 1099.63
#Mann=4,-1,0
  4764.6    0.12       0  4772.7    0.05       0  4977.3    0.05       0
  4984.3    0.05       0
Bank Sta=4977.3,4984.3
Exp/Cntr=0.3,0.1

Type RM Length L Ch R = 1,8585,416,416,416
BEGIN DESCRIPTION:
CEDAR HOLLOW CREEK 19.0
END DESCRIPTION:
XS GIS Cut Line= 3
      2850355.67     10277053.15      2850260.50     10277304.00
      2850305.69     10277553.13
#Sta/Elev= 30
  4731.7 1100.70  4746.7 1099.67  4753.1 1098.22  4771.5 1095.44  4776.9 1095.49
  4801.7 1090.46  4807.0 1090.31  4838.6 1085.58  4849.3 1083.18  4856.6 1080.75
  4861.9 1080.85  4881.4 1077.36  4892.1 1077.31  4911.5 1080.62  4953.7 1081.65
  4966.5 1082.24  4971.8 1081.76  4977.7 1079.89  4996.2 1075.58  4996.7 1075.08
  5002.8 1075.08  5003.3 1075.58  5009.3 1078.54  5019.4 1082.38  5049.9 1082.68
  5090.6 1083.85  5109.5 1084.80  5121.1 1086.05  5202.4 1088.44  5253.2 1090.96
#Mann=4,-1,0
  4731.7    0.12       0  4953.7    0.05       0  4996.2    0.03       0
  5003.3    0.05       0
Bank Sta=4996.2,5003.3
Exp/Cntr=0.3,0.1

Type RM Length L Ch R = 1,8169,499,499,499
BEGIN DESCRIPTION:
CEDAR HOLLOW CREEK 18.0
END DESCRIPTION:
XS GIS Cut Line= 3
      2850005.69     10277153.11      2849894.75     10277306.00
      2849905.68     10277453.09
#Sta/Elev= 30
  4811.1 1090.73  4814.2 1090.73  4818.5 1089.92  4824.6 1089.85  4833.1 1088.66
  4839.3 1088.83  4860.5 1087.99  4883.4 1085.56  4925.1 1082.46  4933.6 1082.07
  4939.8 1082.34  4975.4 1078.70  4983.9 1074.51  4991.6 1072.82  4992.1 1072.32
  4998.2 1072.32  4998.7 1072.82  5007.1 1073.38  5027.2 1077.13  5037.2 1079.98
  5047.2 1083.68  5057.3 1085.41  5067.3 1086.53  5081.2 1087.05  5087.4 1087.97
  5097.4 1087.74  5117.4 1088.01  5127.5 1087.42  5137.5 1088.49  5147.5 1088.79
#Mann=3,-1,0
  4811.1    0.12       0  4991.6    0.07       0  4998.7    0.12       0
Bank Sta=4991.6,4998.7
Exp/Cntr=0.3,0.1

Type RM Length L Ch R = 1,7670,371,371,371
BEGIN DESCRIPTION:
CEDAR HOLLOW CREEK 17.0
END DESCRIPTION:
XS GIS Cut Line= 3
      2849505.67     10277103.13      2849440.25     10277239.00
      2850055.67     10277953.10
#Sta/Elev= 30
  4849.2 1091.09  4925.6 1077.62  4953.8 1076.35  4970.8 1072.79  4976.4 1074.22
  4982.4 1069.89  4989.9 1069.52  4990.4 1069.02  4997.1 1069.52  5034.9 1075.30
  5282.8 1087.54  5368.4 1088.55  5382.6 1085.31  5389.2 1086.88  5396.9 1079.89
  5403.5 1080.98  5411.2 1076.30  5425.4 1076.10  5474.8 1079.70  5517.6 1076.66
  5524.2 1079.29  5531.8 1078.00  5552.7 1082.69  5581.2 1081.80  5602.1 1084.44
  5722.8 1084.31  5744.7 1080.29  5786.0 1087.57  5836.8 1092.13  5942.7 1095.31
#Mann=4,-1,0
  4849.2    0.12       0  4989.9    0.07       0  4997.1    0.12       0
  5786.0    0.05       0
Bank Sta=4989.9,4997.1
Exp/Cntr=0.3,0.1

Type RM Length L Ch R = 1,7299,452,452,452
BEGIN DESCRIPTION:
CEDAR HOLLOW CREEK 16.0
END DESCRIPTION:
XS GIS Cut Line= 3
      2849705.68     10276553.11      2849087.50     10277321.00
      2849505.66     10277753.09
#Sta/Elev= 30
  4014.2 1087.97  4057.2 1087.23  4248.6 1085.18  4348.0 1086.44  4390.9 1084.70
  4512.5 1086.28  4648.5 1082.59  4966.8 1072.92  4998.1 1065.35  5021.4 1065.38
  5028.6 1067.23  5035.5 1065.63  5042.7 1069.98  5045.1 1064.95  5045.6 1064.45
  5054.2 1064.95  5056.9 1068.30  5063.8 1067.08  5071.0 1068.98  5078.0 1067.13
  5085.2 1073.19  5092.1 1069.72  5099.3 1074.97  5106.3 1072.13  5113.5 1075.19
  5120.4 1073.80  5196.6 1077.33  5420.5 1082.29  5444.7 1082.61  5601.3 1086.43
#Mann=8,-1,0
  4014.2    0.12       0  4057.2    0.05       0  4648.5    0.12       0
  5045.1    0.07       0  5054.2    0.12       0  5196.6    0.05       0
  5420.5    0.12       0  5444.7    0.05       0
Bank Sta=5045.1,5054.2
Exp/Cntr=0.3,0.1

Type RM Length L Ch R = 1,6847,463,463,463
BEGIN DESCRIPTION:
CEDAR HOLLOW CREEK 15.0
END DESCRIPTION:
XS GIS Cut Line= 3
      2849005.71     10277053.10      2848666.50     10277166.00
      2848555.65     10277253.14
#Sta/Elev= 30
  4642.5 1079.02  4674.1 1079.79  4690.0 1078.97  4721.6 1079.40  4737.4 1078.72
  4800.6 1078.13  4821.8 1077.40  4832.2 1076.19  4848.2 1076.88  4853.5 1074.90
  4879.8 1073.69  4885.1 1072.33  4921.2 1071.41  4958.7 1071.55  4969.2 1070.36
  4974.8 1068.58  4980.0 1066.06  5000.6 1062.89  5001.1 1062.39  5009.8 1062.39
  5010.3 1062.89  5013.5 1063.37  5019.9 1067.03  5026.5 1066.96  5055.1 1070.83
  5084.0 1072.79  5098.5 1075.20  5104.8 1075.39  5119.3 1078.12  5141.0 1079.84
#Mann=4,-1,0
  4642.5    0.12       0  4921.2    0.05       0  5000.6    0.05       0
  5010.3    0.05       0
Bank Sta=5000.6,5010.3
Exp/Cntr=0.3,0.1

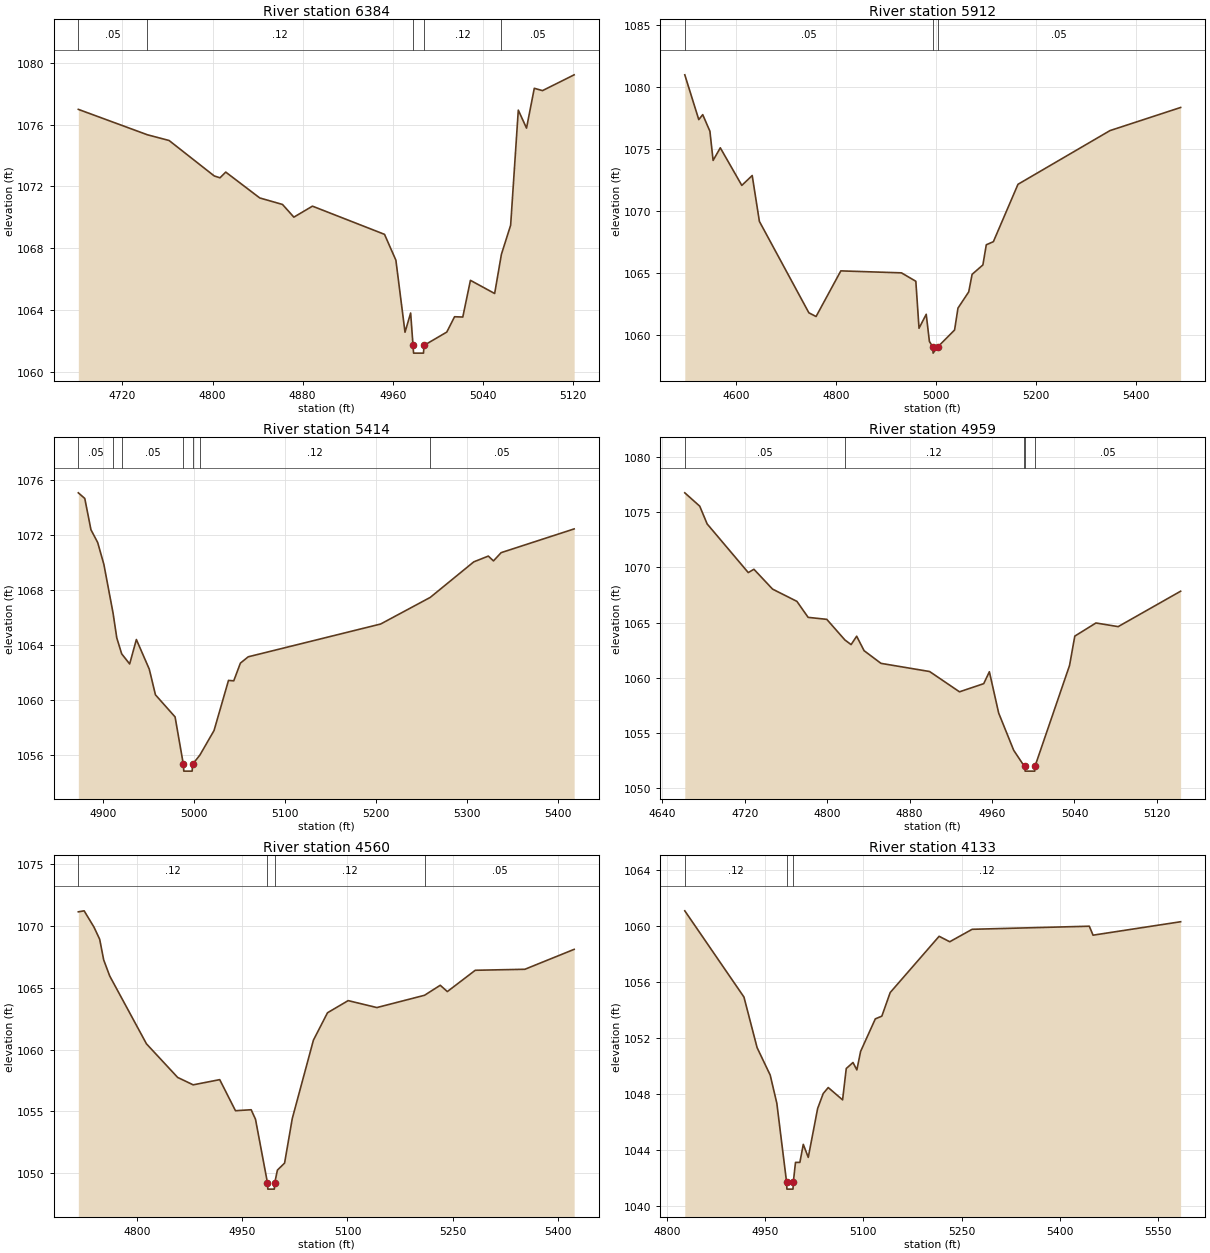
Type RM Length L Ch R = 1,6384,472,472,472
BEGIN DESCRIPTION:
CEDAR HOLLOW CREEK 14.0
END DESCRIPTION:
XS GIS Cut Line= 3
      2848705.67     10276853.11      2848388.75     10276815.00
      2848305.68     10276903.12
#Sta/Elev= 30
  4680.8 1076.98  4742.1 1075.34  4761.4 1074.97  4801.5 1072.68  4806.6 1072.56
  4811.7 1072.93  4841.9 1071.26  4862.1 1070.84  4872.2 1070.02  4888.7 1070.73
  4952.7 1068.91  4962.8 1067.24  4970.9 1062.59  4975.9 1063.83  4978.0 1061.74
  4978.5 1061.24  4987.3 1061.24  4987.8 1061.74  5008.0 1062.60  5014.9 1063.59
  5022.2 1063.57  5029.0 1065.94  5050.5 1065.09  5056.5 1067.62  5064.7 1069.50
  5071.5 1076.93  5078.8 1075.77  5085.7 1078.34  5093.0 1078.19  5121.1 1079.21
#Mann=5,-1,0
  4680.8    0.05       0  4742.1    0.12       0  4978.0    0.07       0
  4987.8    0.12       0  5056.5    0.05       0
Bank Sta=4978,4987.8
Exp/Cntr=0.3,0.1

Type RM Length L Ch R = 1,5912,498,498,498
BEGIN DESCRIPTION:
CEDAR HOLLOW CREEK 13.0
END DESCRIPTION:
XS GIS Cut Line= 3
      2848705.66     10275953.14      2848388.75     10276344.00
      2848055.68     10276703.12
#Sta/Elev= 30
  4496.8 1081.01  4524.8 1077.39  4532.7 1077.79  4547.1 1076.45  4553.5 1074.09
  4567.9 1075.11  4611.0 1072.07  4631.8 1072.87  4646.2 1069.16  4745.3 1061.77
  4759.7 1061.47  4809.3 1065.16  4930.7 1065.00  4959.5 1064.32  4965.9 1060.52
  4980.3 1061.65  4986.7 1059.45  4993.6 1059.01  4994.1 1058.51  5003.4 1059.01
  5037.1 1060.38  5043.9 1062.15  5065.4 1063.46  5072.2 1064.88  5093.8 1065.64
  5100.6 1067.27  5114.8 1067.52  5164.1 1072.16  5348.3 1076.50  5489.8 1078.37
#Mann=3,-1,0
  4496.8    0.05       0  4993.6    0.05       0  5003.4    0.05       0
Bank Sta=4993.6,5003.4
Exp/Cntr=0.3,0.1

Type RM Length L Ch R = 1,5414,455,455,455
BEGIN DESCRIPTION:
CEDAR HOLLOW CREEK 12.0
END DESCRIPTION:
XS GIS Cut Line= 3
      2848405.72     10275803.08      2848311.25     10275889.00
      2848105.70     10276253.08
#Sta/Elev= 30
  4872.3 1075.07  4879.4 1074.66  4886.2 1072.38  4893.6 1071.45  4900.4 1069.86
  4910.5 1066.32  4914.6 1064.51  4920.0 1063.34  4928.8 1062.60  4936.2 1064.38
  4950.4 1062.22  4957.2 1060.35  4978.8 1058.74  4987.9 1055.29  4988.4 1054.79
  4997.6 1054.79  4998.1 1055.29  5006.2 1055.97  5021.7 1057.75  5037.6 1061.40
  5043.4 1061.37  5050.7 1062.66  5059.3 1063.12  5205.1 1065.51  5259.7 1067.45
  5307.6 1070.04  5323.6 1070.46  5329.3 1070.11  5337.7 1070.71  5418.1 1072.44
#Mann=7,-1,0
  4872.3    0.05       0  4910.5    0.12       0  4920.0    0.05       0
  4987.9    0.05       0  4998.1    0.05       0  5006.2    0.12       0
  5259.7    0.05       0
Bank Sta=4987.9,4998.1
Exp/Cntr=0.3,0.1

Type RM Length L Ch R = 1,4959,399,399,399
BEGIN DESCRIPTION:
CEDAR HOLLOW CREEK 11.0
END DESCRIPTION:
XS GIS Cut Line= 3
      2848005.68     10275603.13      2847872.50     10275914.00
      2847905.68     10276053.10
#Sta/Elev= 30
  4661.8 1076.76  4676.3 1075.55  4683.5 1073.94  4723.4 1069.53  4728.9 1069.83
  4747.0 1068.03  4770.6 1066.92  4781.5 1065.47  4799.6 1065.29  4817.2 1063.42
  4823.2 1063.00  4828.6 1063.76  4835.8 1062.45  4852.2 1061.30  4899.4 1060.56
  4928.4 1058.72  4951.9 1059.46  4957.4 1060.54  4966.4 1056.80  4981.0 1053.42
  4990.8 1052.04  4991.6 1052.03  4992.1 1051.53  5001.4 1051.53  5001.9 1052.03
  5035.2 1061.11  5040.3 1063.77  5060.8 1064.96  5082.4 1064.63  5143.0 1067.84
#Mann=5,-1,0
  4661.8    0.05       0  4817.2    0.12       0  4990.8    0.05       0
  4991.6    0.03       0  5001.9    0.05       0
Bank Sta=4991.6,5001.9
Exp/Cntr=0.3,0.1

Type RM Length L Ch R = 1,4560,427,427,427
BEGIN DESCRIPTION:
CEDAR HOLLOW CREEK 10.0
END DESCRIPTION:
XS GIS Cut Line= 3
      2847805.66     10275553.12      2847552.25     10275682.00
      2847505.68     10276103.13
#Sta/Elev= 30
  4715.7 1071.12  4724.0 1071.20  4738.1 1069.88  4746.2 1068.90  4751.9 1067.24
  4760.5 1065.94  4813.0 1060.46  4857.5 1057.75  4879.7 1057.15  4917.6 1057.57
  4940.1 1055.06  4962.5 1055.14  4968.7 1054.37  4985.8 1049.23  4986.3 1048.73
  4995.6 1048.73  4996.1 1049.23  5000.0 1050.27  5010.2 1050.83  5021.2 1054.43
  5051.4 1060.76  5071.5 1062.97  5101.0 1063.95  5142.0 1063.39  5210.0 1064.38
  5232.5 1065.19  5242.6 1064.68  5282.5 1066.40  5353.3 1066.48  5423.7 1068.09
#Mann=4,-1,0
  4715.7    0.12       0  4985.8    0.07       0  4996.1    0.12       0
  5210.0    0.05       0
Bank Sta=4985.8,4996.1
Exp/Cntr=0.3,0.1

Type RM Length L Ch R = 1,4133,481,481,481
BEGIN DESCRIPTION:
CEDAR HOLLOW CREEK 9.0
END DESCRIPTION:
XS GIS Cut Line= 3
      2847605.67     10275303.11      2847433.75     10275289.00
      2847155.68     10275803.12
#Sta/Elev= 30
  4827.5 1061.08  4917.8 1054.92  4937.9 1051.30  4957.9 1049.34  4968.0 1047.33
  4982.9 1041.69  4983.4 1041.19  4992.7 1041.19  4993.2 1041.69  4996.5 1043.10
  5003.2 1043.10  5008.4 1044.39  5016.0 1043.46  5030.3 1046.95  5038.8 1048.02
  5046.5 1048.45  5068.4 1047.57  5074.0 1049.81  5084.3 1050.24  5090.2 1049.71
  5095.9 1051.03  5118.4 1053.36  5128.3 1053.55  5141.1 1055.24  5215.8 1059.26
  5232.0 1058.87  5266.2 1059.76  5445.1 1059.98  5450.8 1059.34  5584.5 1060.30
#Mann=3,-1,0
  4827.5    0.12       0  4982.9    0.07       0  4993.2    0.12       0
Bank Sta=4982.9,4993.2
Exp/Cntr=0.3,0.1

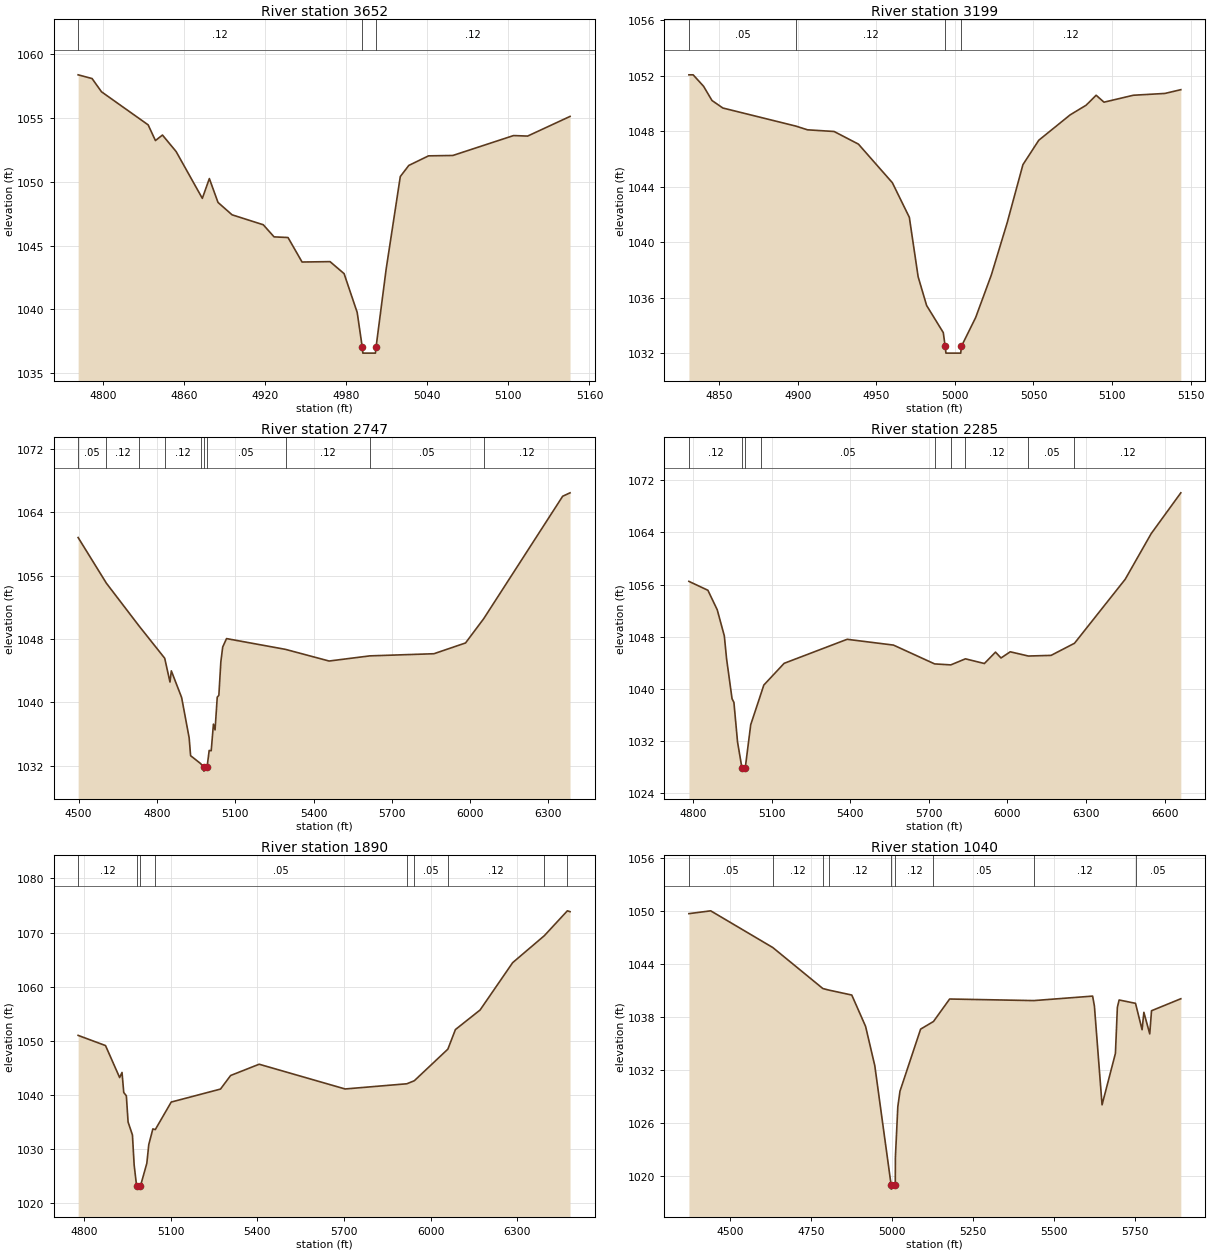
Type RM Length L Ch R = 1,3652,453,453,453
BEGIN DESCRIPTION:
CEDAR HOLLOW CREEK 8.0
END DESCRIPTION:
XS GIS Cut Line= 3
      2847305.67     10274803.15      2847248.75     10275014.00
      2847205.69     10275153.09
#Sta/Elev= 30
  4781.6 1058.39  4791.9 1058.10  4798.9 1057.06  4833.4 1054.47  4838.8 1053.24
  4844.0 1053.67  4854.1 1052.38  4873.5 1048.71  4878.7 1050.26  4885.1 1048.39
  4895.5 1047.42  4918.6 1046.64  4926.6 1045.69  4936.9 1045.64  4947.3 1043.72
  4968.0 1043.75  4978.4 1042.81  4988.1 1039.77  4991.8 1037.08  4992.3 1036.58
  5001.6 1036.58  5002.1 1037.08  5009.5 1043.14  5020.0 1050.42  5026.3 1051.29
  5040.9 1052.04  5058.9 1052.07  5103.8 1053.63  5114.2 1053.59  5145.6 1055.13
#Mann=3,-1,0
  4781.6    0.12       0  4991.8    0.07       0  5002.1    0.12       0
Bank Sta=4991.8,5002.1
Exp/Cntr=0.3,0.1

Type RM Length L Ch R = 1,3199,452,452,452
BEGIN DESCRIPTION:
CEDAR HOLLOW CREEK 7.0
END DESCRIPTION:
XS GIS Cut Line= 3
      2846955.68     10274603.13      2846892.00     10274760.00
      2846905.69     10274903.15
#Sta/Elev= 30
  4830.7 1052.06  4833.4 1052.06  4840.0 1051.24  4845.4 1050.21  4852.3 1049.67
  4898.7 1048.37  4906.2 1048.10  4923.1 1047.98  4938.6 1047.07  4960.2 1044.29
  4971.0 1041.80  4976.6 1037.52  4982.0 1035.45  4992.6 1033.50  4993.8 1032.52
  4994.3 1032.02  5003.7 1032.02  5004.2 1032.52  5013.2 1034.58  5023.2 1037.65
  5033.3 1041.42  5043.3 1045.59  5053.4 1047.35  5073.4 1049.18  5083.5 1049.87
  5089.9 1050.59  5094.9 1050.09  5113.6 1050.59  5133.7 1050.72  5143.8 1050.99
#Mann=4,-1,0
  4830.7    0.05       0  4898.7    0.12       0  4993.8    0.07       0
  5004.2    0.12       0
Bank Sta=4993.8,5004.2
Exp/Cntr=0.3,0.1

Type RM Length L Ch R = 1,2747,462,462,462
BEGIN DESCRIPTION:
CEDAR HOLLOW CREEK 6.0
END DESCRIPTION:
XS GIS Cut Line= 3
      2847055.67     10274353.12      2846571.75     10274487.00
      2845455.70     10275303.10
#Sta/Elev= 30
  4497.9 1060.80  4606.1 1055.04  4730.7 1049.67  4829.6 1045.57  4849.8 1042.57
  4855.0 1043.98  4894.5 1040.61  4923.3 1035.52  4928.8 1033.28  4966.9 1032.29
  4979.1 1031.83  4979.6 1031.33  4991.9 1031.83  5000.0 1033.94  5007.8 1033.90
  5016.3 1037.26  5022.5 1036.53  5030.9 1040.66  5037.1 1040.90  5044.7 1045.12
  5051.8 1046.99  5066.5 1048.05  5292.5 1046.69  5459.5 1045.22  5615.4 1045.87
  5861.0 1046.14  5982.2 1047.50  6052.0 1050.57  6354.4 1066.01  6382.6 1066.44
#Mann=10,-1,0
  4497.9    0.05       0  4606.1    0.12       0  4730.7    0.05       0
  4829.6    0.12       0  4966.9    0.05       0  4979.1    0.03       0
  4991.9    0.05       0  5292.5    0.12       0  5615.4    0.05       0
  6052.0    0.12       0
Bank Sta=4979.1,4991.9
Exp/Cntr=0.3,0.1

Type RM Length L Ch R = 1,2285,395,395,395
BEGIN DESCRIPTION:
CEDAR HOLLOW CREEK 5.0
END DESCRIPTION:
XS GIS Cut Line= 3
      2846755.66     10273903.14      2846630.25     10274079.00
      2845405.67     10275203.12
#Sta/Elev= 30
  4784.0 1056.49  4856.5 1055.12  4892.1 1052.13  4919.2 1048.12  4927.8 1044.60
  4948.7 1038.46  4955.9 1037.89  4969.6 1031.84  4986.4 1027.84  4986.9 1027.34
  4999.2 1027.84  5020.0 1034.47  5057.5 1039.03  5070.0 1040.56  5147.6 1043.90
  5388.1 1047.59  5565.1 1046.70  5722.2 1043.81  5784.1 1043.66  5839.9 1044.59
  5912.2 1043.87  5954.7 1045.62  5975.7 1044.72  6010.9 1045.67  6080.3 1045.02
  6166.9 1045.12  6256.3 1046.98  6449.9 1056.81  6549.1 1063.82  6662.3 1070.09
#Mann=9,-1,0
  4784.0    0.12       0  4986.4    0.07       0  4999.2    0.12       0
  5057.5    0.05       0  5722.2    0.12       0  5784.1    0.05       0
  5839.9    0.12       0  6080.3    0.05       0  6256.3    0.12       0
Bank Sta=4986.4,4999.2
Exp/Cntr=0.3,0.1

Type RM Length L Ch R = 1,1890,850,850,850
BEGIN DESCRIPTION:
CEDAR HOLLOW CREEK 4.0
END DESCRIPTION:
XS GIS Cut Line= 3
      2846455.70     10273803.10      2846271.00     10273925.00
      2845155.65     10274903.14
#Sta/Elev= 30
  4778.7 1051.00  4873.6 1049.12  4922.5 1043.21  4930.8 1044.15  4936.8 1040.45
  4945.8 1039.83  4951.8 1035.00  4966.9 1032.60  4972.9 1027.03  4981.5 1023.09
  4982.0 1022.59  4994.3 1023.09  5016.8 1027.37  5023.5 1030.82  5037.7 1033.72
  5046.1 1033.59  5101.3 1038.68  5272.1 1041.08  5307.2 1043.59  5406.1 1045.67
  5703.9 1041.10  5918.0 1042.06  5943.8 1042.62  6060.1 1048.46  6086.3 1052.08
  6171.7 1055.69  6284.6 1064.44  6394.5 1069.43  6474.2 1074.02  6483.5 1073.87
#Mann=9,-1,0
  4778.7    0.12       0  4981.5    0.07       0  4994.3    0.12       0
  5046.1    0.05       0  5918.0    0.12       0  5943.8    0.05       0
  6060.1    0.12       0  6394.5    0.05       0  6474.2    0.12       0
Bank Sta=4981.5,4994.3
Exp/Cntr=0.3,0.1

Type RM Length L Ch R = 1,1040,782,782,782
BEGIN DESCRIPTION:
Mapping XS 770ea202
END DESCRIPTION:
XS GIS Cut Line= 4
      2846382.81     10273350.89      2845955.95     10273337.34
      2845712.02     10273560.93      2845414.04     10274258.48
#Sta/Elev= 30
  4373.8 1049.74  4441.0 1050.06  4632.5 1045.89  4786.7 1041.24  4804.3 1041.07
  4875.9 1040.50  4918.5 1036.94  4946.8 1032.49  4997.1 1018.97  4997.6 1018.47
  5010.0 1018.97  5010.4 1022.11  5017.8 1027.81  5024.5 1029.59  5088.1 1036.63
  5127.8 1037.50  5177.6 1040.05  5437.0 1039.87  5618.4 1040.38  5623.9 1039.25
  5647.5 1028.04  5688.7 1033.88  5694.7 1039.11  5700.1 1039.94  5750.6 1039.56
  5770.9 1036.56  5776.4 1038.54  5794.5 1036.09  5800.0 1038.72  5890.3 1040.08
#Mann=9,-1,0
  4373.8    0.05       0  4632.5    0.12       0  4786.7    0.05       0
  4804.3    0.12       0  4997.1    0.07       0  5010.0    0.12       0
  5127.8    0.05       0  5437.0    0.12       0  5750.6    0.05       0
Bank Sta=4997.1,5010
Exp/Cntr=0.3,0.1

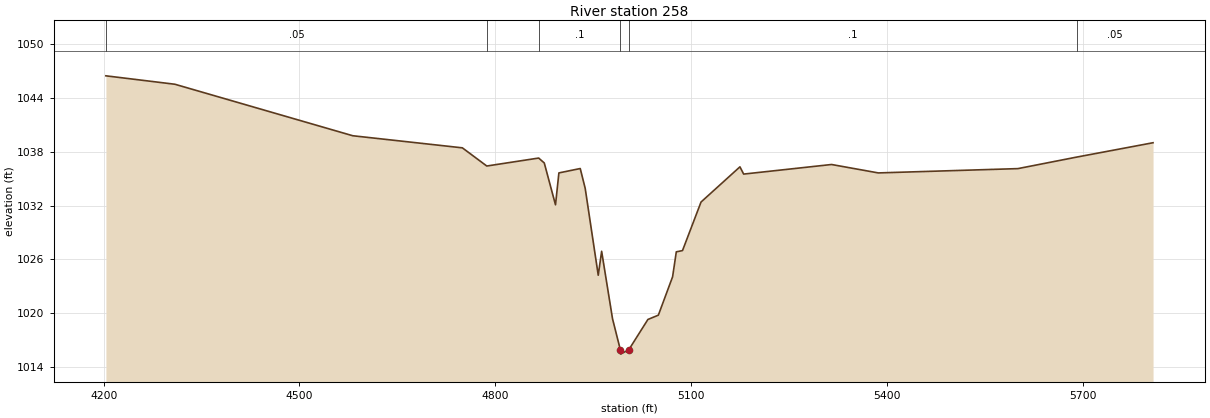
Type RM Length L Ch R = 1,258,0,0,0
BEGIN DESCRIPTION:
CEDAR HOLLOW CREEK 2.0
END DESCRIPTION:
XS GIS Cut Line= 3
      2846287.95     10273100.20      2845526.25     10272867.00
      2845136.11     10273574.46
#Sta/Elev= 30
  4203.4 1046.50  4309.1 1045.56  4581.7 1039.81  4749.6 1038.46  4787.0 1036.43
  4866.5 1037.32  4875.1 1036.77  4892.3 1032.10  4897.5 1035.66  4930.2 1036.15
  4937.8 1033.94  4957.8 1024.24  4963.0 1026.91  4979.7 1019.37  4991.6 1015.93
  4992.1 1015.43  5004.7 1015.93  5033.9 1019.30  5049.9 1019.78  5071.7 1024.06
  5077.4 1026.85  5086.9 1026.99  5115.3 1032.41  5174.9 1036.34  5180.6 1035.53
  5315.3 1036.60  5386.9 1035.66  5600.8 1036.14  5691.1 1037.43  5807.9 1039.03
#Mann=6,-1,0
  4203.4    0.05       0  4787.0    0.12       0  4866.5     0.1       0
  4991.6    0.07       0  5004.7     0.1       0  5691.1    0.05       0
Bank Sta=4991.6,5004.7
Exp/Cntr=0.3,0.1

Chan Stop Cuts=-1