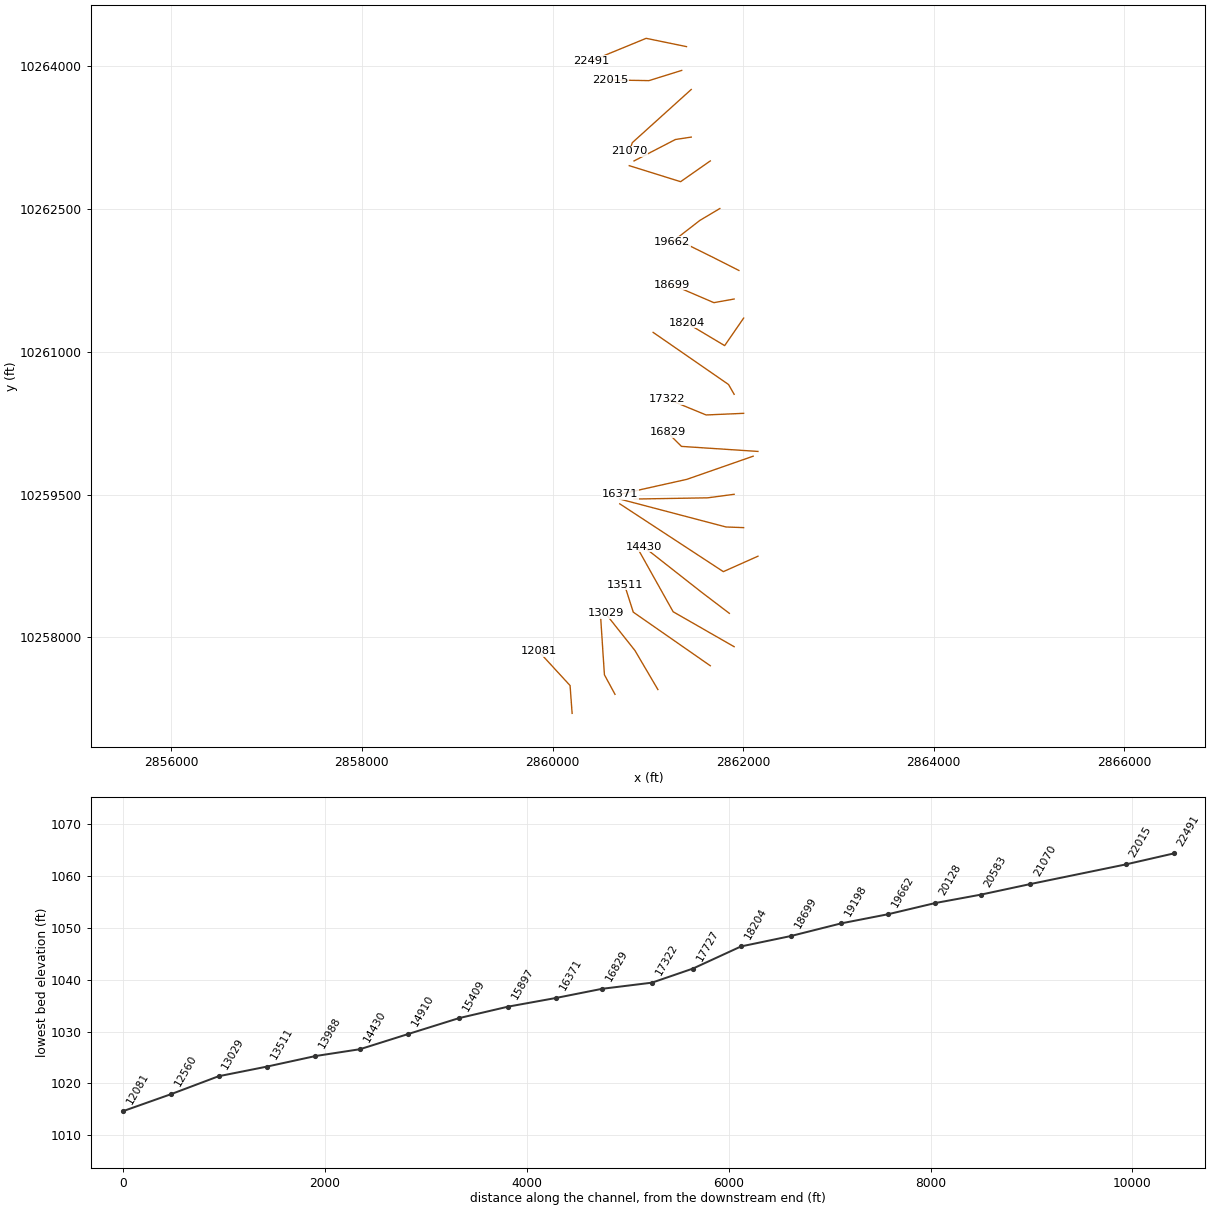
HEC-RAS study HARRIS BRANCH.prj: HARRIS BRANCH Base Level Engineering

--- HARRIS BRANCH.g01 (geometry) --- (continued)

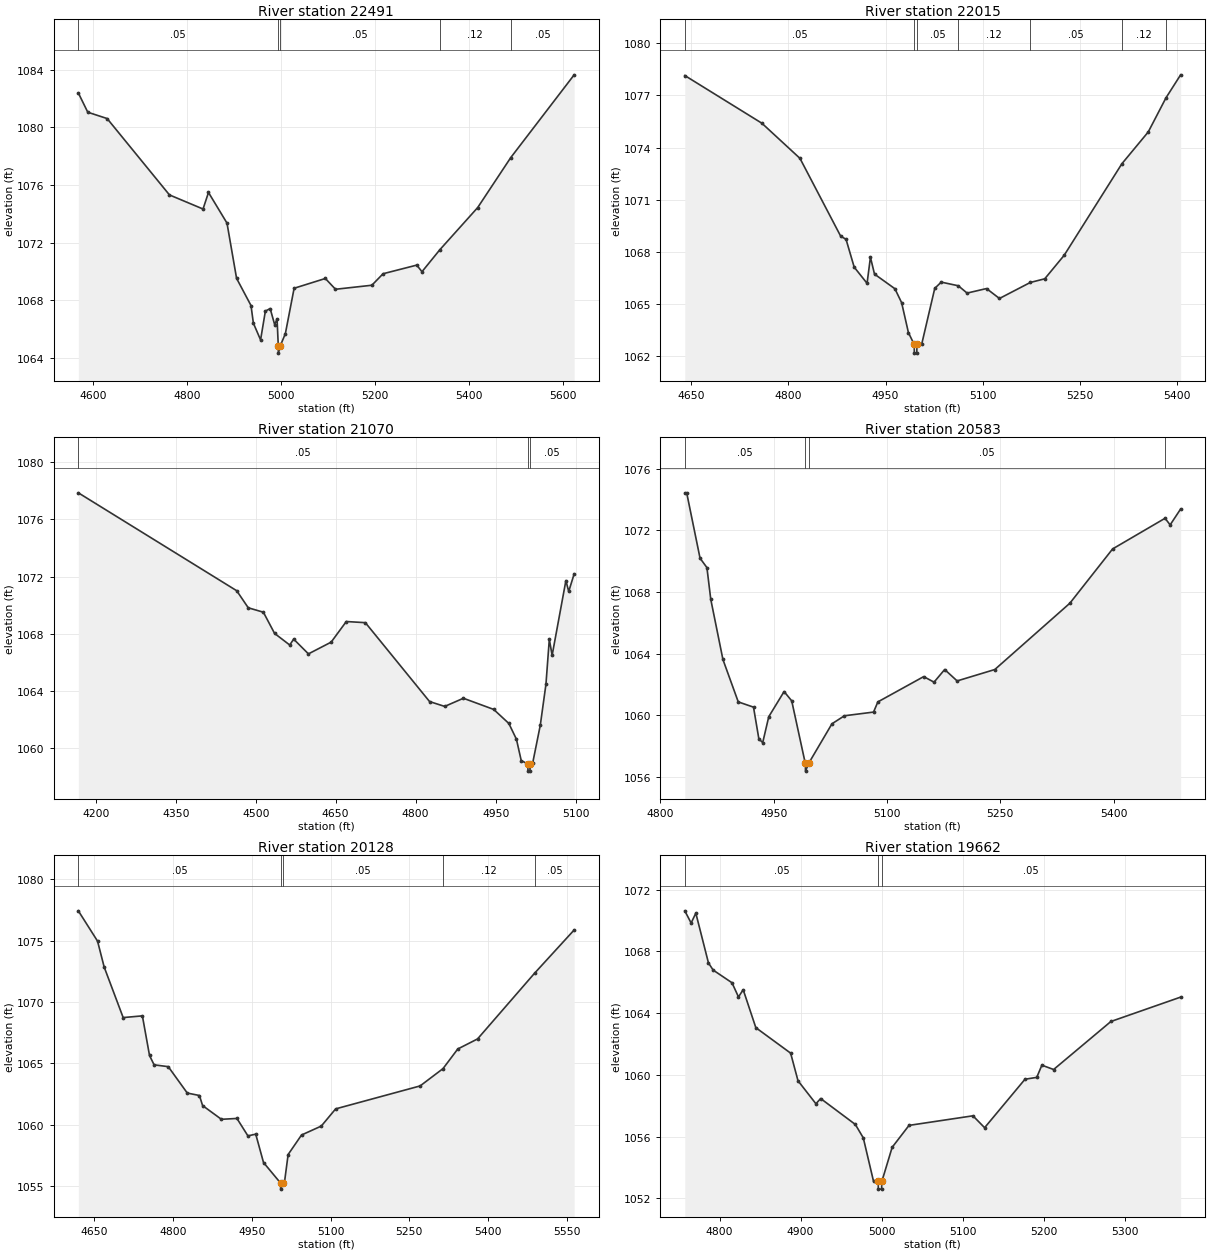
Type RM Length L Ch R = 1,22491,476,476,476
BEGIN DESCRIPTION:
HARRIS BRANCH 43.0
END DESCRIPTION:
XS GIS Cut Line= 3
      2861405.72     10264203.11      2860982.75     10264290.00
      2860405.68     10264053.11
#Sta/Elev= 30
  4568.2 1082.40  4588.3 1081.06  4629.5 1080.62  4762.2 1075.31  4833.7 1074.33
  4845.3 1075.48  4884.7 1073.35  4905.1 1069.51  4935.8 1067.62  4940.9 1066.39
  4956.2 1065.23  4966.4 1067.23  4976.6 1067.41  4986.2 1066.29  4991.3 1066.69
  4993.9 1064.81  4994.1 1064.31  4998.1 1064.81  5009.0 1065.67  5027.6 1068.82
  5094.1 1069.50  5115.7 1068.75  5193.1 1069.03  5217.0 1069.83  5288.7 1070.43
  5299.8 1069.97  5337.6 1071.49  5418.4 1074.43  5488.7 1077.90  5623.8 1083.66
#Mann=5,-1,0
  4568.2    0.05       0  4993.9    0.05       0  4998.1    0.05       0
  5337.6    0.12       0  5488.7    0.05       0
Bank Sta=4993.9,4998.1
Exp/Cntr=0.3,0.1

Type RM Length L Ch R = 1,22015,945,945,945
BEGIN DESCRIPTION:
HARRIS BRANCH 42.0
END DESCRIPTION:
XS GIS Cut Line= 3
      2861355.66     10263953.10      2861011.75     10263846.00
      2860605.71     10263853.11
#Sta/Elev= 30
  4639.8 1078.14  4758.9 1075.40  4817.8 1073.38  4880.7 1068.91  4889.0 1068.73
  4901.6 1067.13  4921.5 1066.20  4926.7 1067.70  4933.0 1066.73  4964.5 1065.89
  4974.9 1065.09  4985.4 1063.37  4994.3 1062.69  4994.6 1062.19  4998.3 1062.19
  4998.6 1062.69  5006.1 1062.73  5026.1 1065.91  5036.1 1066.27  5062.5 1066.06
  5076.1 1065.64  5106.1 1065.90  5126.1 1065.33  5173.8 1066.25  5196.1 1066.46
  5226.1 1067.81  5315.3 1073.07  5356.1 1074.90  5383.5 1076.86  5406.1 1078.18
#Mann=7,-1,0
  4639.8    0.05       0  4994.3    0.05       0  4998.6    0.05       0
  5062.5    0.12       0  5173.8    0.05       0  5315.3    0.12       0
  5383.5    0.05       0
Bank Sta=4994.3,4998.6
Exp/Cntr=0.3,0.1

Type RM Length L Ch R = 1,21070,487,487,487
BEGIN DESCRIPTION:
HARRIS BRANCH 41.0
END DESCRIPTION:
XS GIS Cut Line= 3
      2861455.71     10263753.13      2860837.75     10263195.00
      2860805.69     10263103.13
#Sta/Elev= 30
  4167.3 1077.85  4464.4 1071.01  4486.0 1069.82  4514.4 1069.51  4535.4 1068.03
  4563.8 1067.22  4571.2 1067.63  4598.9 1066.60  4641.5 1067.42  4669.9 1068.86
  4705.7 1068.78  4826.1 1063.27  4854.5 1062.93  4889.6 1063.50  4946.4 1062.72
  4974.8 1061.74  4989.0 1060.64  4998.0 1059.15  5010.4 1058.91  5010.7 1058.41
  5014.4 1058.41  5014.7 1058.91  5019.7 1059.01  5033.8 1061.62  5044.4 1064.48
  5050.7 1067.62  5056.0 1066.50  5081.8 1071.72  5087.1 1070.96  5097.3 1072.19
#Mann=3,-1,0
  4167.3    0.05       0  5010.4    0.05       0  5014.7    0.05       0
Bank Sta=5010.4,5014.7
Exp/Cntr=0.3,0.1

Type RM Length L Ch R = 1,20583,455,455,455
BEGIN DESCRIPTION:
HARRIS BRANCH 40.0
END DESCRIPTION:
XS GIS Cut Line= 3
      2861455.66     10263253.11      2861289.75     10263228.00
      2860855.65     10263003.10
#Sta/Elev= 30
  4832.2 1074.43  4834.7 1074.43  4852.4 1070.19  4861.5 1069.58  4866.6 1067.52
  4882.7 1063.62  4903.0 1060.87  4923.2 1060.53  4930.3 1058.47  4935.4 1058.23
  4943.4 1059.91  4963.7 1061.54  4973.8 1060.94  4991.8 1056.88  4992.1 1056.38
  4996.2 1056.88  5027.1 1059.45  5043.6 1059.97  5082.2 1060.21  5087.9 1060.87
  5148.6 1062.51  5162.3 1062.15  5176.4 1062.97  5192.9 1062.23  5242.8 1062.97
  5342.2 1067.27  5398.8 1070.79  5468.3 1072.78  5475.0 1072.35  5488.9 1073.38
#Mann=4,-1,0
  4832.2    0.05       0  4991.8    0.05       0  4996.2    0.05       0
  5468.3    0.12       0
Bank Sta=4991.8,4996.2
Exp/Cntr=0.3,0.1

Type RM Length L Ch R = 1,20128,466,466,466
BEGIN DESCRIPTION:
HARRIS BRANCH 39.0
END DESCRIPTION:
XS GIS Cut Line= 3
      2861655.67     10263003.10      2861344.00     10262785.00
      2860805.64     10262953.12
#Sta/Elev= 30
  4619.6 1077.43  4656.2 1074.96  4668.8 1072.85  4705.0 1068.73  4741.6 1068.87
  4755.2 1065.64  4763.9 1064.88  4790.9 1064.73  4827.1 1062.58  4850.2 1062.38
  4856.3 1061.56  4892.1 1060.44  4921.7 1060.51  4942.6 1059.09  4957.5 1059.23
  4972.3 1056.92  5004.7 1055.25  5005.0 1054.75  5009.2 1055.25  5012.2 1055.29
  5019.2 1057.57  5044.7 1059.16  5082.4 1059.89  5109.7 1061.29  5270.6 1063.16
  5314.2 1064.57  5342.3 1066.17  5380.0 1066.99  5488.7 1072.35  5564.0 1075.87
#Mann=5,-1,0
  4619.6    0.05       0  5004.7    0.05       0  5009.2    0.05       0
  5314.2    0.12       0  5488.7    0.05       0
Bank Sta=5004.7,5009.2
Exp/Cntr=0.3,0.1

Type RM Length L Ch R = 1,19662,464,464,464
BEGIN DESCRIPTION:
HARRIS BRANCH 38.0
END DESCRIPTION:
XS GIS Cut Line= 3
      2861755.68     10262503.11      2861547.00     10262379.00
      2861255.71     10262153.13
#Sta/Elev= 30
  4757.2 1070.63  4765.0 1069.84  4770.8 1070.48  4786.4 1067.25  4792.2 1066.79
  4815.4 1065.97  4823.4 1065.05  4829.2 1065.52  4844.8 1063.06  4887.7 1061.41
  4896.8 1059.62  4918.9 1058.13  4924.7 1058.47  4967.5 1056.79  4977.3 1055.92
  4989.9 1053.11  4995.6 1053.10  4995.9 1052.60  4999.8 1052.60  5000.2 1053.10
  5012.9 1055.31  5033.7 1056.73  5112.5 1057.35  5126.9 1056.58  5176.7 1059.72
  5191.2 1059.84  5197.5 1060.63  5212.0 1060.35  5282.6 1063.46  5368.6 1065.04
#Mann=3,-1,0
  4757.2    0.05       0  4995.6    0.05       0  5000.2    0.05       0
Bank Sta=4995.6,5000.2
Exp/Cntr=0.3,0.1

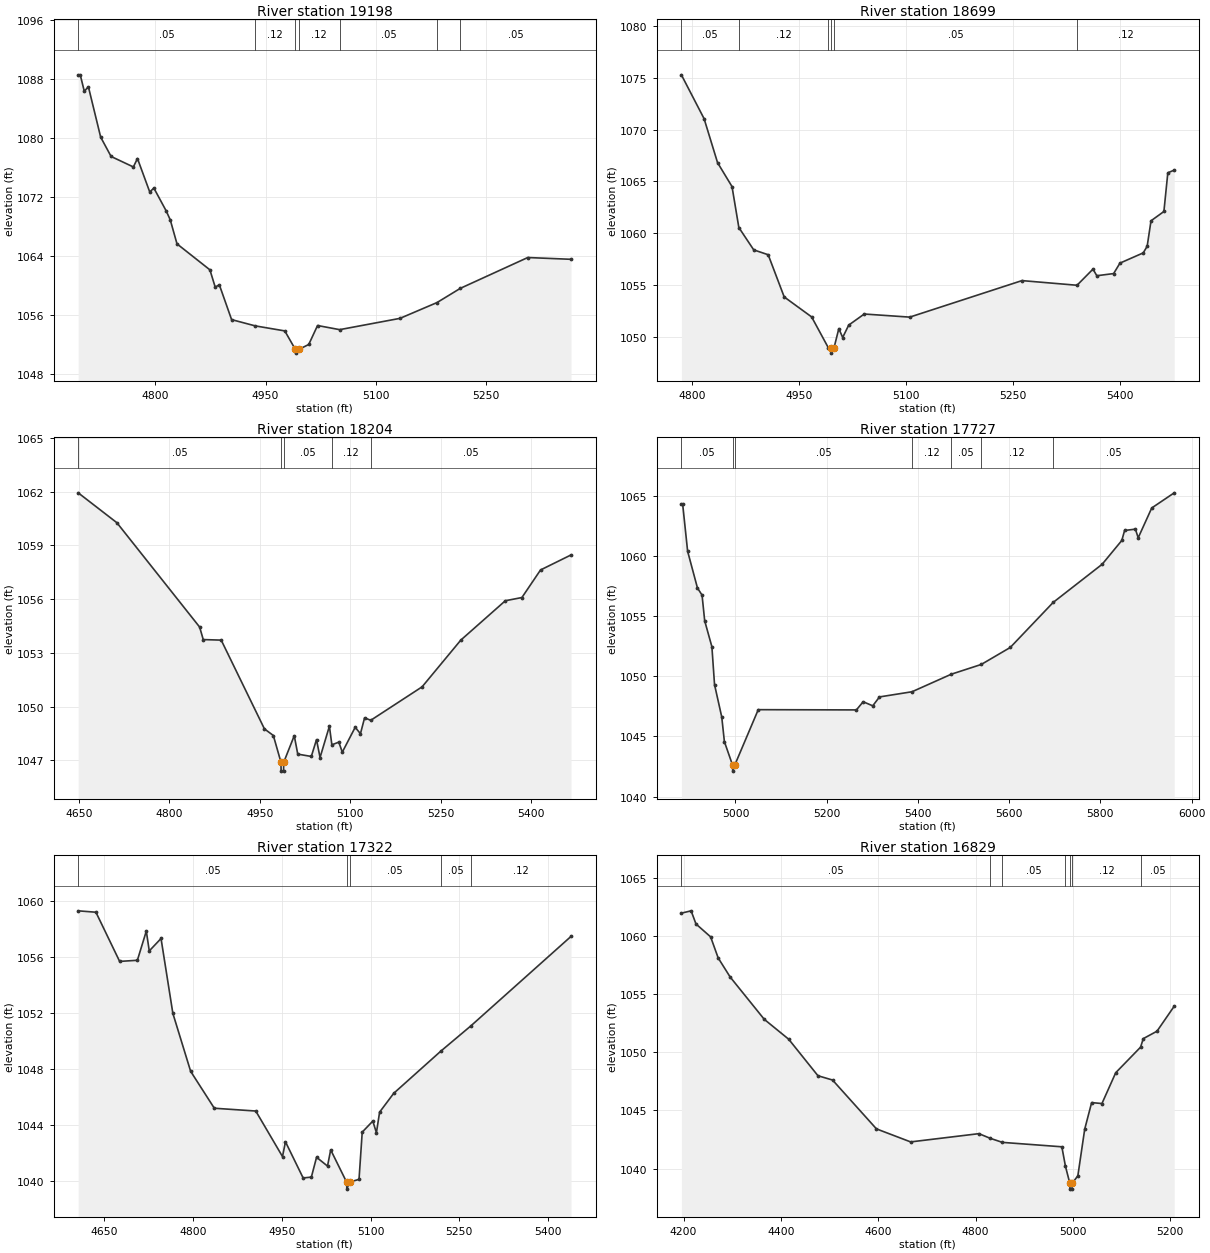
Type RM Length L Ch R = 1,19198,499,499,499
BEGIN DESCRIPTION:
HARRIS BRANCH 37.0
END DESCRIPTION:
XS GIS Cut Line= 3
      2861955.67     10261853.12      2861683.50     10261991.00
      2861355.69     10262153.11
#Sta/Elev= 30
  4694.9 1088.54  4697.7 1088.54  4703.2 1086.32  4708.8 1086.92  4725.5 1080.10
  4739.7 1077.48  4770.0 1076.06  4775.6 1077.20  4792.3 1072.67  4797.9 1073.20
  4814.6 1070.12  4820.2 1068.90  4829.4 1065.64  4874.2 1062.12  4881.4 1059.78
  4887.0 1060.10  4903.7 1055.38  4935.9 1054.53  4976.1 1053.85  4990.5 1051.34
  4990.8 1050.84  4995.1 1051.34  5008.7 1052.01  5020.7 1054.58  5050.8 1054.02
  5132.9 1055.55  5183.3 1057.69  5215.1 1059.62  5306.8 1063.79  5365.7 1063.55
#Mann=7,-1,0
  4694.9    0.05       0  4935.9    0.12       0  4990.5    0.07       0
  4995.1    0.12       0  5050.8    0.05       0  5183.3    0.12       0
  5215.1    0.05       0
Bank Sta=4990.5,4995.1
Exp/Cntr=0.3,0.1

Type RM Length L Ch R = 1,18699,495,495,495
BEGIN DESCRIPTION:
HARRIS BRANCH 36.0
END DESCRIPTION:
XS GIS Cut Line= 3
      2861905.70     10261553.12      2861693.50     10261515.00
      2861255.70     10261703.10
#Sta/Elev= 30
  4784.4 1075.30  4816.3 1071.06  4835.2 1066.81  4855.5 1064.50  4865.1 1060.54
  4886.0 1058.38  4906.3 1057.91  4928.8 1053.83  4967.3 1051.90  4990.6 1048.94
  4994.1 1048.90  4994.4 1048.40  4998.7 1048.90  5005.5 1050.77  5010.9 1049.91
  5019.4 1051.11  5041.2 1052.18  5105.1 1051.88  5262.7 1055.41  5340.0 1054.96
  5362.4 1056.52  5367.8 1055.88  5391.4 1056.09  5400.3 1057.10  5433.0 1058.09
  5438.5 1058.73  5443.9 1061.19  5462.0 1062.09  5467.5 1065.83  5476.5 1066.09
#Mann=6,-1,0
  4784.4    0.05       0  4865.1    0.12       0  4990.6    0.05       0
  4994.1    0.05       0  4998.7    0.05       0  5340.0    0.12       0
Bank Sta=4994.1,4998.7
Exp/Cntr=0.3,0.1

Type RM Length L Ch R = 1,18204,477,477,477
BEGIN DESCRIPTION:
HARRIS BRANCH 35.0
END DESCRIPTION:
XS GIS Cut Line= 3
      2862005.67     10261353.09      2861806.25     10261064.00
      2861405.69     10261303.11
#Sta/Elev= 30
  4648.8 1061.94  4713.0 1060.27  4850.3 1054.44  4856.3 1053.74  4886.1 1053.71
  4957.8 1048.75  4972.6 1048.38  4985.2 1046.89  4985.5 1046.39  4989.5 1046.39
  4989.9 1046.89  5007.3 1048.37  5013.1 1047.34  5035.6 1047.21  5044.2 1048.15
  5050.1 1047.15  5065.6 1048.90  5069.7 1047.86  5081.2 1048.01  5087.0 1047.45
  5108.4 1048.84  5117.1 1048.48  5124.0 1049.37  5134.2 1049.23  5219.4 1051.10
  5283.6 1053.71  5357.5 1055.91  5385.0 1056.09  5415.9 1057.63  5466.5 1058.47
#Mann=5,-1,0
  4648.8    0.05       0  4985.2    0.05       0  4989.9    0.05       0
  5069.7    0.12       0  5134.2    0.05       0
Bank Sta=4985.2,4989.9
Exp/Cntr=0.3,0.1

Type RM Length L Ch R = 1,17727,405,405,405
BEGIN DESCRIPTION:
HARRIS BRANCH 34.0
END DESCRIPTION:
XS GIS Cut Line= 3
      2861905.70     10260553.09      2861846.75     10260656.00
      2861055.71     10261203.09
#Sta/Elev= 30
  4881.4 1064.29  4884.3 1064.29  4895.1 1060.40  4916.7 1057.34  4926.7 1056.76
  4932.5 1054.62  4948.3 1052.46  4954.1 1049.31  4969.9 1046.62  4975.7 1044.57
  4993.6 1042.62  4994.0 1042.12  4998.4 1042.62  5049.9 1047.23  5265.1 1047.21
  5279.9 1047.89  5300.9 1047.55  5315.7 1048.29  5387.0 1048.72  5473.2 1050.18
  5538.8 1050.99  5602.3 1052.40  5696.5 1056.15  5803.8 1059.32  5846.9 1061.30
  5853.0 1062.13  5876.7 1062.24  5882.8 1061.52  5912.5 1064.00  5961.8 1065.26
#Mann=7,-1,0
  4881.4    0.05       0  4993.6    0.05       0  4998.4    0.05       0
  5387.0    0.12       0  5473.2    0.05       0  5538.8    0.12       0
  5696.5    0.05       0
Bank Sta=4993.6,4998.4
Exp/Cntr=0.3,0.1

Type RM Length L Ch R = 1,17322,493,493,493
BEGIN DESCRIPTION:
HARRIS BRANCH 33.0
END DESCRIPTION:
XS GIS Cut Line= 3
      2862005.68     10260353.11      2861611.75     10260336.00
      2861205.69     10260503.11
#Sta/Elev= 30
  4605.7 1059.33  4635.7 1059.23  4675.8 1055.71  4705.8 1055.79  4720.9 1057.88
  4725.9 1056.46  4745.8 1057.35  4765.8 1051.99  4795.9 1047.84  4835.9 1045.20
  4906.0 1045.00  4951.2 1041.74  4956.2 1042.80  4986.1 1040.21  5000.0 1040.27
  5008.8 1041.69  5027.3 1041.06  5032.7 1042.22  5059.6 1039.91  5060.0 1039.41
  5064.5 1039.91  5080.6 1040.11  5086.0 1043.49  5103.9 1044.28  5110.0 1043.45
  5115.4 1044.92  5139.3 1046.27  5219.0 1049.29  5269.6 1051.09  5439.1 1057.50
#Mann=5,-1,0
  4605.7    0.05       0  5059.6    0.05       0  5064.5    0.05       0
  5219.0    0.05       0  5269.6    0.12       0
Bank Sta=5059.6,5064.5
Exp/Cntr=0.3,0.1

Type RM Length L Ch R = 1,16829,458,458,458
BEGIN DESCRIPTION:
HARRIS BRANCH 32.0
END DESCRIPTION:
XS GIS Cut Line= 3
      2862155.66     10259953.11      2861353.00     10260006.00
      2861205.68     10260153.12
#Sta/Elev= 30
  4195.6 1061.96  4215.6 1062.16  4225.6 1061.03  4255.7 1059.92  4271.2 1058.11
  4295.8 1056.47  4365.9 1052.83  4416.1 1051.12  4476.2 1047.98  4506.2 1047.61
  4596.4 1043.41  4666.6 1042.29  4806.9 1043.00  4830.1 1042.60  4855.2 1042.25
  4977.3 1041.87  4984.8 1040.18  4993.7 1038.73  4994.0 1038.23  4998.2 1038.23
  4998.6 1038.73  5010.2 1039.38  5024.3 1043.39  5038.5 1045.67  5059.7 1045.59
  5088.0 1048.24  5139.1 1050.44  5144.6 1051.17  5172.8 1051.81  5208.2 1053.96
#Mann=7,-1,0
  4195.6    0.05       0  4830.1    0.12       0  4855.2    0.05       0
  4984.8    0.12       0  4993.7    0.07       0  4998.6    0.12       0
  5139.1    0.05       0
Bank Sta=4993.7,4998.6
Exp/Cntr=0.3,0.1

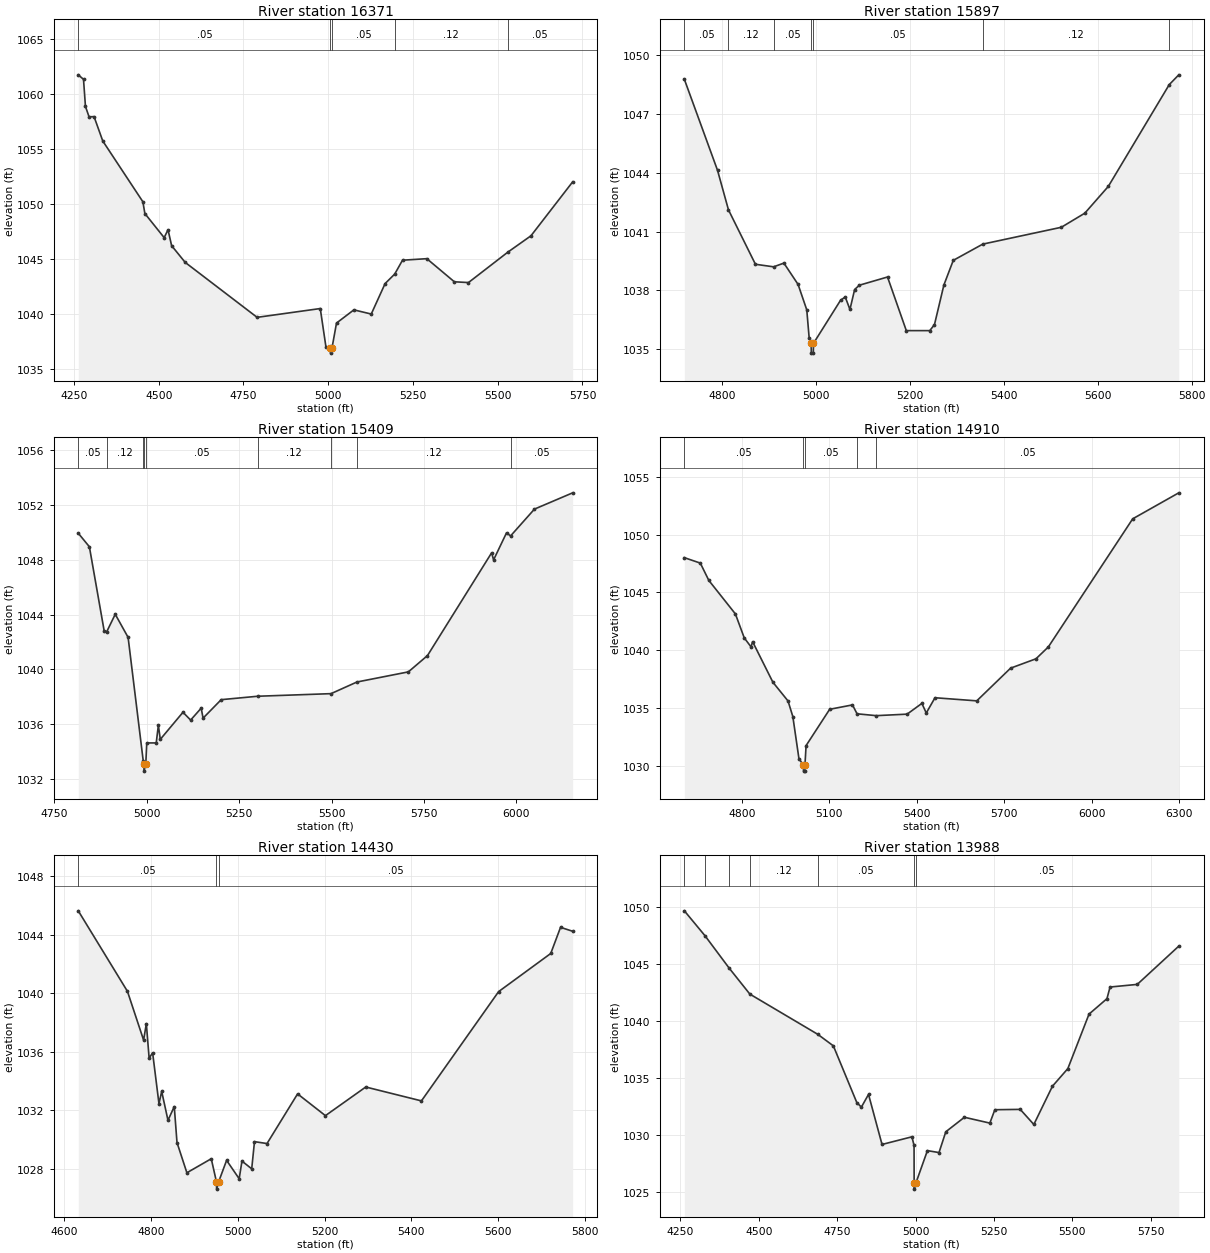
Type RM Length L Ch R = 1,16371,474,474,474
BEGIN DESCRIPTION:
HARRIS BRANCH 31.0
END DESCRIPTION:
XS GIS Cut Line= 3
      2862105.67     10259903.11      2861409.50     10259660.00
      2860705.67     10259503.11
#Sta/Elev= 30
  4262.6 1061.74  4278.1 1061.33  4283.8 1058.87  4294.4 1057.93  4309.2 1057.94
  4334.9 1055.73  4453.2 1050.21  4459.1 1049.14  4516.0 1046.95  4527.4 1047.67
  4538.0 1046.22  4578.1 1044.70  4790.2 1039.71  4976.5 1040.51  4993.4 1036.99
  5006.4 1036.96  5006.8 1036.46  5011.3 1036.96  5024.4 1039.19  5075.6 1040.39
  5126.9 1040.01  5167.8 1042.78  5196.1 1043.64  5219.1 1044.90  5290.8 1045.04
  5372.0 1042.94  5413.7 1042.87  5529.7 1045.63  5598.1 1047.12  5721.1 1052.02
#Mann=5,-1,0
  4262.6    0.05       0  5006.4    0.03       0  5011.3    0.05       0
  5196.1    0.12       0  5529.7    0.05       0
Bank Sta=5006.4,5011.3
Exp/Cntr=0.3,0.1

Type RM Length L Ch R = 1,15897,488,488,488
BEGIN DESCRIPTION:
HARRIS BRANCH 30.0
END DESCRIPTION:
XS GIS Cut Line= 3
      2861905.68     10259503.11      2861628.25     10259466.00
      2860855.66     10259453.11
#Sta/Elev= 30
  4720.1 1048.78  4790.7 1044.13  4814.0 1042.11  4871.4 1039.33  4910.1 1039.20
  4932.0 1039.39  4962.2 1038.30  4980.7 1037.00  4985.8 1035.56  4990.0 1035.29
  4990.4 1034.79  4994.6 1034.79  4995.0 1035.29  5052.6 1037.49  5062.6 1037.66
  5072.6 1037.02  5082.6 1038.04  5092.6 1038.26  5152.6 1038.68  5192.6 1035.94
  5242.6 1035.94  5252.6 1036.25  5272.6 1038.27  5292.6 1039.53  5355.4 1040.36
  5522.6 1041.22  5572.6 1041.94  5622.7 1043.31  5752.4 1048.51  5772.7 1049.01
#Mann=7,-1,0
  4720.1    0.05       0  4814.0    0.12       0  4910.1    0.05       0
  4990.0    0.03       0  4995.0    0.05       0  5355.4    0.12       0
  5752.4    0.05       0
Bank Sta=4990,4995
Exp/Cntr=0.3,0.1

Type RM Length L Ch R = 1,15409,499,499,499
BEGIN DESCRIPTION:
HARRIS BRANCH 29.0
END DESCRIPTION:
XS GIS Cut Line= 3
      2862005.72     10259153.11      2861820.25     10259160.00
      2860705.65     10259453.12
#Sta/Elev= 30
  4814.4 1049.95  4844.5 1048.96  4884.5 1042.82  4891.4 1042.75  4914.5 1044.03
  4949.3 1042.34  4990.4 1033.28  4992.1 1033.07  4992.4 1032.57  4997.1 1033.07
  4999.8 1034.63  5025.4 1034.63  5031.2 1035.92  5036.4 1034.89  5097.8 1036.87
  5118.5 1036.30  5147.1 1037.17  5152.2 1036.44  5201.2 1037.79  5299.9 1038.04
  5498.5 1038.23  5568.6 1039.08  5707.8 1039.82  5759.5 1041.01  5933.2 1048.52
  5938.4 1048.00  5973.5 1049.98  5984.4 1049.75  6049.0 1051.71  6152.5 1052.90
#Mann=9,-1,0
  4814.4    0.05       0  4891.4    0.12       0  4990.4    0.05       0
  4992.1    0.03       0  4997.1    0.05       0  5299.9    0.12       0
  5498.5    0.05       0  5568.6    0.12       0  5984.4    0.05       0
Bank Sta=4992.1,4997.1
Exp/Cntr=0.3,0.1

Type RM Length L Ch R = 1,14910,480,480,480
BEGIN DESCRIPTION:
HARRIS BRANCH 28.0
END DESCRIPTION:
XS GIS Cut Line= 3
      2862155.66     10258853.10      2861792.50     10258691.00
      2860705.71     10259403.09
#Sta/Elev= 30
  4602.3 1048.00  4657.0 1047.53  4686.3 1046.03  4777.5 1043.13  4807.8 1041.06
  4831.1 1040.28  4836.5 1040.73  4906.2 1037.22  4958.1 1035.60  4974.6 1034.25
  4995.5 1030.62  5011.1 1030.03  5011.4 1029.53  5015.7 1029.53  5016.1 1030.03
  5020.1 1031.74  5101.0 1034.88  5179.3 1035.26  5195.0 1034.49  5260.9 1034.33
  5366.8 1034.46  5417.5 1035.39  5432.6 1034.56  5462.5 1035.88  5605.9 1035.61
  5722.0 1038.44  5809.2 1039.25  5851.7 1040.28  6141.1 1051.36  6299.3 1053.61
#Mann=5,-1,0
  4602.3    0.05       0  5011.1    0.03       0  5016.1    0.05       0
  5195.0    0.12       0  5260.9    0.05       0
Bank Sta=5011.1,5016.1
Exp/Cntr=0.3,0.1

Type RM Length L Ch R = 1,14430,442,442,442
BEGIN DESCRIPTION:
HARRIS BRANCH 27.0
END DESCRIPTION:
XS GIS Cut Line= 3
      2861855.69     10258253.11      2861562.75     10258476.00
      2860955.70     10258953.10
#Sta/Elev= 30
  4631.9 1045.64  4745.3 1040.13  4782.6 1036.79  4788.9 1037.92  4795.3 1035.56
  4803.4 1035.92  4818.0 1032.44  4824.3 1033.28  4838.8 1031.30  4853.3 1032.24
  4859.6 1029.78  4882.4 1027.71  4938.6 1028.67  4950.6 1027.09  4951.0 1026.59
  4955.6 1027.09  4974.0 1028.56  5003.0 1027.30  5009.4 1028.51  5031.9 1027.98
  5038.3 1029.84  5067.2 1029.71  5137.7 1033.11  5201.9 1031.62  5294.9 1033.58
  5423.3 1032.63  5601.3 1040.11  5721.5 1042.72  5744.1 1044.51  5772.1 1044.24
#Mann=3,-1,0
  4631.9    0.05       0  4950.6    0.05       0  4955.6    0.05       0
Bank Sta=4950.6,4955.6
Exp/Cntr=0.3,0.1

Type RM Length L Ch R = 1,13988,477,477,477
BEGIN DESCRIPTION:
HARRIS BRANCH 26.0
END DESCRIPTION:
XS GIS Cut Line= 3
      2861905.64     10257903.13      2861265.75     10258270.00
      2860855.69     10259003.11
#Sta/Elev= 30
  4262.4 1049.63  4328.5 1047.44  4404.9 1044.63  4471.4 1042.34  4688.1 1038.82
  4737.8 1037.81  4812.6 1032.85  4827.2 1032.45  4850.0 1033.56  4893.1 1029.18
  4988.5 1029.85  4995.3 1029.09  4995.6 1025.77  4996.0 1025.27  5000.7 1025.77
  5037.9 1028.64  5074.9 1028.47  5096.6 1030.29  5156.0 1031.56  5237.1 1031.05
  5253.1 1032.22  5334.1 1032.25  5377.5 1030.93  5436.9 1034.28  5486.0 1035.82
  5553.6 1040.59  5610.8 1041.94  5620.7 1042.96  5707.5 1043.19  5840.0 1046.54
#Mann=7,-1,0
  4262.4    0.05       0  4328.5    0.12       0  4404.9    0.05       0
  4471.4    0.12       0  4688.1    0.05       0  4995.6    0.03       0
  5000.7    0.05       0
Bank Sta=4995.6,5000.7
Exp/Cntr=0.3,0.1

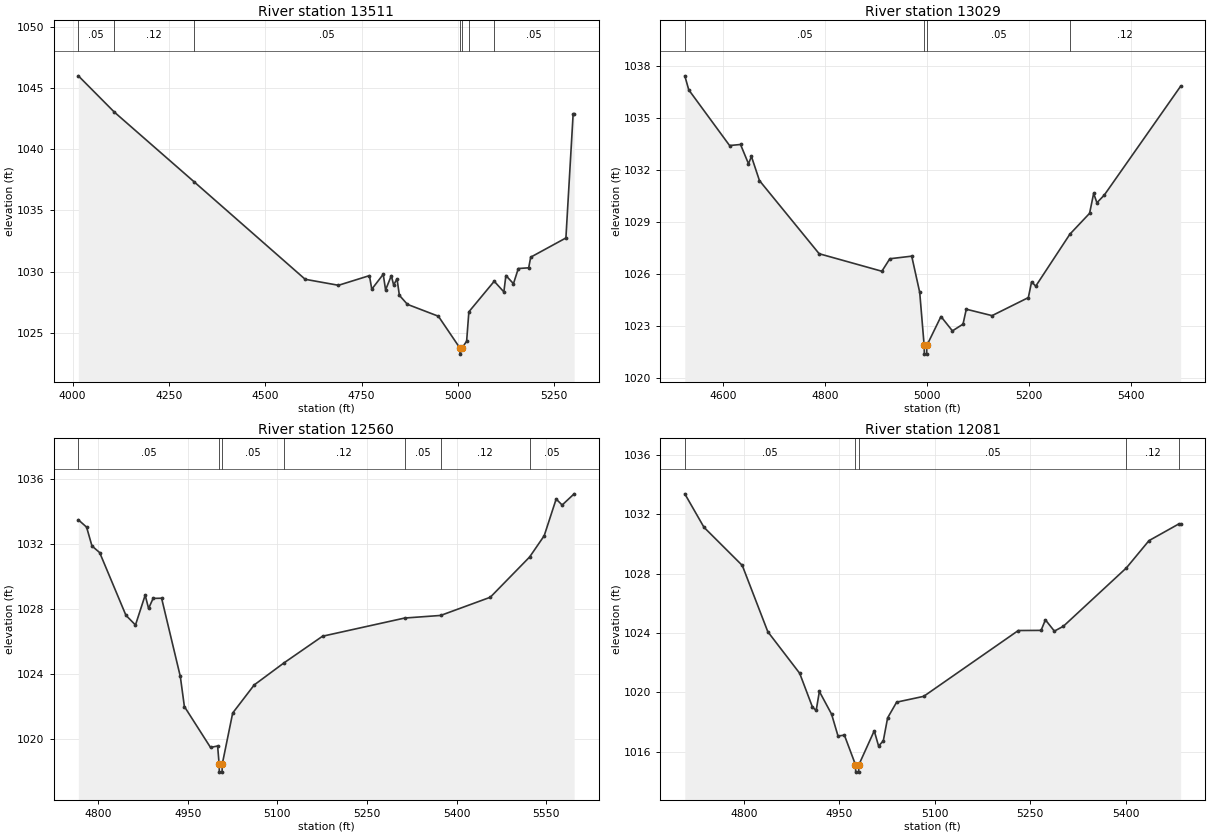
Type RM Length L Ch R = 1,13511,482,482,482
BEGIN DESCRIPTION:
HARRIS BRANCH 25.0
END DESCRIPTION:
XS GIS Cut Line= 3
      2861655.69     10257703.11      2860847.25     10258266.00
      2860755.67     10258553.15
#Sta/Elev= 30
  4014.9 1046.01  4108.1 1043.05  4315.4 1037.34  4603.5 1029.37  4689.9 1028.88
  4770.2 1029.67  4776.3 1028.56  4806.0 1029.78  4812.1 1028.50  4827.0 1029.67
  4833.0 1028.90  4841.8 1029.41  4847.9 1028.06  4868.8 1027.32  4949.1 1026.35
  5004.9 1023.75  5005.3 1023.25  5010.1 1023.75  5022.4 1024.30  5028.2 1026.71
  5094.0 1029.21  5119.0 1028.34  5124.3 1029.68  5143.9 1029.01  5156.5 1030.25
  5183.4 1030.31  5188.7 1031.18  5280.0 1032.75  5298.7 1042.86  5301.4 1042.86
#Mann=7,-1,0
  4014.9    0.05       0  4108.1    0.12       0  4315.4    0.05       0
  5004.9    0.05       0  5010.1    0.05       0  5028.2    0.12       0
  5094.0    0.05       0
Bank Sta=5004.9,5010.1
Exp/Cntr=0.3,0.1

Type RM Length L Ch R = 1,13029,469,469,469
BEGIN DESCRIPTION:
HARRIS BRANCH 24.0
END DESCRIPTION:
XS GIS Cut Line= 3
      2861105.67     10257453.14      2860865.00     10257863.00
      2860555.66     10258253.14
#Sta/Elev= 30
  4524.7 1037.43  4532.5 1036.62  4612.6 1033.41  4634.1 1033.47  4649.7 1032.36
  4655.5 1032.78  4671.2 1031.39  4788.4 1027.17  4911.5 1026.16  4927.1 1026.88
  4970.1 1027.03  4985.8 1024.94  4994.5 1021.88  4994.9 1021.38  4999.4 1021.38
  4999.8 1021.88  5027.5 1023.55  5050.0 1022.72  5070.8 1023.11  5077.2 1023.97
  5127.8 1023.60  5199.0 1024.64  5205.4 1025.55  5213.5 1025.30  5280.6 1028.30
  5319.2 1029.50  5327.2 1030.65  5333.6 1030.11  5348.0 1030.55  5497.9 1036.83
#Mann=4,-1,0
  4524.7    0.05       0  4994.5    0.03       0  4999.8    0.05       0
  5280.6    0.12       0
Bank Sta=4994.5,4999.8
Exp/Cntr=0.3,0.1

Type RM Length L Ch R = 1,12560,479,479,479
BEGIN DESCRIPTION:
HARRIS BRANCH 23.0
END DESCRIPTION:
XS GIS Cut Line= 3
      2860655.69     10257403.11      2860544.75     10257608.00
      2860505.68     10258203.12
#Sta/Elev= 30
  4767.0 1033.48  4780.8 1033.03  4789.8 1031.87  4802.7 1031.46  4846.6 1027.60
  4862.6 1027.00  4878.8 1028.84  4884.5 1028.02  4892.1 1028.64  4906.3 1028.65
  4937.6 1023.83  4944.4 1021.98  4988.1 1019.46  5000.0 1019.55  5002.5 1018.44
  5002.9 1017.94  5007.4 1017.94  5007.8 1018.44  5025.2 1021.58  5061.2 1023.31
  5110.7 1024.66  5175.5 1026.31  5312.9 1027.43  5373.1 1027.59  5456.1 1028.71
  5521.9 1031.19  5546.3 1032.50  5566.3 1034.76  5576.3 1034.39  5596.4 1035.08
#Mann=7,-1,0
  4767.0    0.05       0  5002.5    0.03       0  5007.8    0.05       0
  5110.7    0.12       0  5312.9    0.05       0  5373.1    0.12       0
  5521.9    0.05       0
Bank Sta=5002.5,5007.8
Exp/Cntr=0.3,0.1

Type RM Length L Ch R = 1,12081,473,473,473
BEGIN DESCRIPTION:
HARRIS BRANCH 22.0
END DESCRIPTION:
XS GIS Cut Line= 3
      2860205.69     10257203.07      2860184.50     10257495.00
      2859855.67     10257853.13
#Sta/Elev= 30
  4707.3 1033.37  4737.4 1031.12  4797.6 1028.55  4837.7 1024.09  4887.8 1021.29
  4907.9 1019.01  4913.7 1018.79  4918.7 1020.07  4937.9 1018.54  4948.0 1017.07
  4958.0 1017.13  4975.4 1015.14  4975.8 1014.64  4980.3 1014.64  4980.8 1015.14
  5004.9 1017.42  5011.7 1016.40  5019.1 1016.74  5025.9 1018.29  5040.1 1019.35
  5082.6 1019.74  5231.2 1024.17  5267.0 1024.18  5273.8 1024.89  5287.9 1024.13
  5302.1 1024.46  5400.9 1028.38  5436.5 1030.22  5483.2 1031.34  5486.2 1031.34
#Mann=5,-1,0
  4707.3    0.05       0  4975.4    0.05       0  4980.8    0.05       0
  5400.9    0.12       0  5483.2    0.05       0
Bank Sta=4975.4,4980.8
Exp/Cntr=0.3,0.1