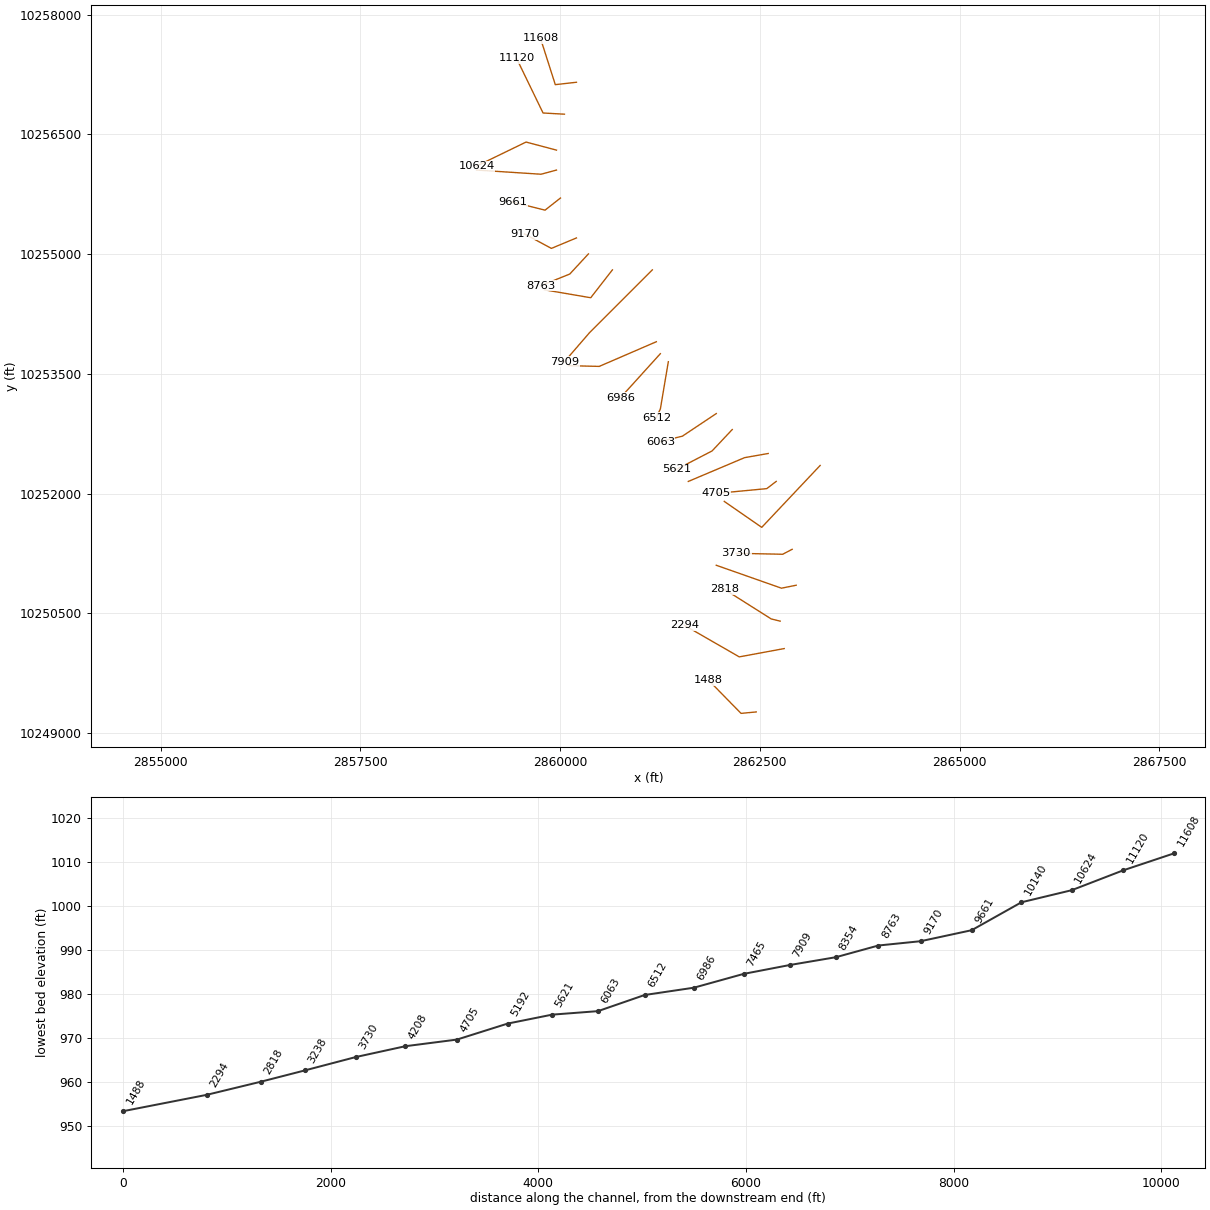
HEC-RAS study HARRIS BRANCH.prj: HARRIS BRANCH Base Level Engineering

--- HARRIS BRANCH.g01 (geometry) --- (continued)

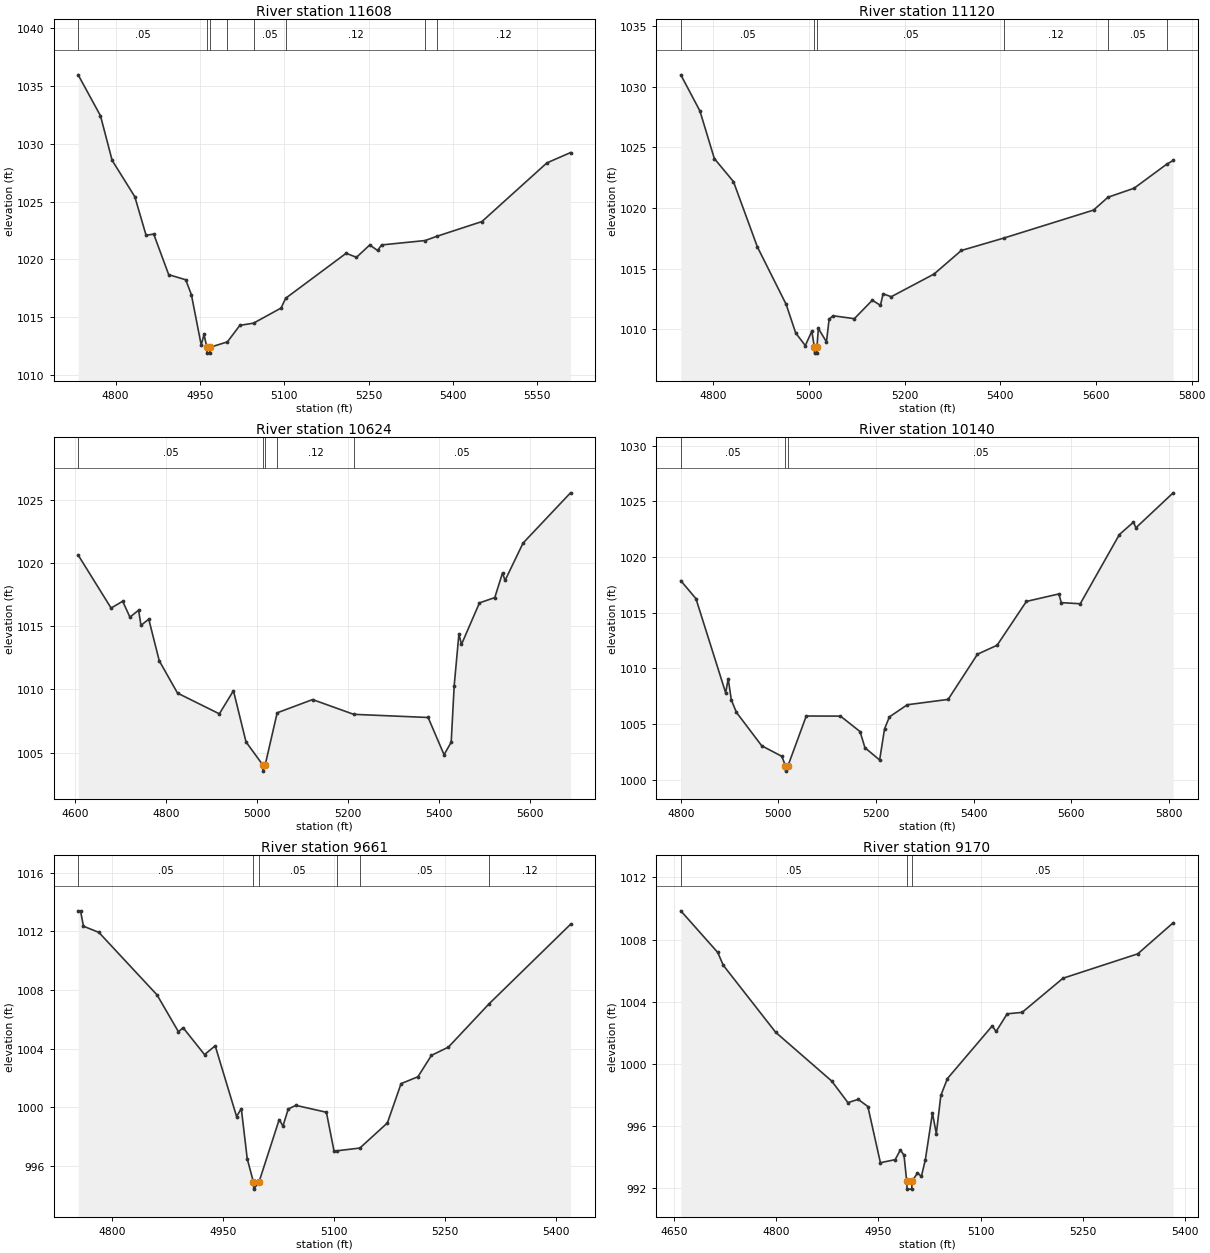
Type RM Length L Ch R = 1,11608,488,488,488
BEGIN DESCRIPTION:
HARRIS BRANCH 21.0
END DESCRIPTION:
XS GIS Cut Line= 3
      2860205.69     10257153.11      2859941.00     10257123.00
      2859755.68     10257703.12
#Sta/Elev= 30
  4733.6 1035.95  4773.3 1032.41  4794.0 1028.56  4834.3 1025.42  4854.4 1022.08
  4867.9 1022.19  4894.6 1018.68  4924.8 1018.24  4934.9 1016.96  4952.4 1012.60
  4957.4 1013.52  4962.4 1012.40  4962.8 1011.90  4967.4 1011.90  4967.8 1012.40
  4998.9 1012.87  5021.1 1014.30  5045.4 1014.49  5094.5 1015.80  5102.5 1016.64
  5210.1 1020.53  5228.4 1020.18  5252.1 1021.25  5265.9 1020.77  5273.1 1021.25
  5350.6 1021.63  5371.0 1021.99  5451.5 1023.27  5567.0 1028.34  5609.0 1029.23
#Mann=8,-1,0
  4733.6    0.05       0  4962.4    0.07       0  4967.8    0.05       0
  4998.9    0.12       0  5045.4    0.05       0  5102.5    0.12       0
  5350.6    0.05       0  5371.0    0.12       0
Bank Sta=4962.4,4967.8
Exp/Cntr=0.3,0.1

Type RM Length L Ch R = 1,11120,496,496,496
BEGIN DESCRIPTION:
HARRIS BRANCH 20.0
END DESCRIPTION:
XS GIS Cut Line= 3
      2860055.64     10256753.11      2859787.75     10256768.00
      2859455.70     10257453.07
#Sta/Elev= 30
  4731.7 1030.99  4771.7 1028.01  4801.8 1024.09  4841.8 1022.19  4891.9 1016.80
  4952.0 1012.07  4972.0 1009.71  4992.1 1008.67  5005.7 1009.86  5011.0 1008.55
  5011.4 1008.05  5016.0 1008.05  5016.5 1008.55  5019.3 1010.09  5036.3 1008.98
  5041.9 1010.85  5050.1 1011.13  5094.6 1010.89  5132.2 1012.41  5149.2 1011.99
  5154.7 1012.94  5171.8 1012.70  5261.3 1014.57  5318.3 1016.51  5407.7 1017.54
  5594.8 1019.84  5625.0 1020.90  5679.5 1021.64  5748.0 1023.63  5761.3 1023.93
#Mann=6,-1,0
  4731.7    0.05       0  5011.0    0.05       0  5016.5    0.05       0
  5407.7    0.12       0  5625.0    0.05       0  5748.0    0.12       0
Bank Sta=5011,5016.5
Exp/Cntr=0.3,0.1

Type RM Length L Ch R = 1,10624,484,484,484
BEGIN DESCRIPTION:
HARRIS BRANCH 19.0
END DESCRIPTION:
XS GIS Cut Line= 3
      2859955.70     10256303.11      2859575.25     10256404.00
      2858955.65     10256103.10
#Sta/Elev= 30
  4606.4 1020.65  4678.8 1016.45  4704.3 1016.99  4720.2 1015.73  4739.3 1016.28
  4744.5 1015.08  4761.6 1015.57  4784.7 1012.27  4824.9 1009.71  4916.8 1008.07
  4947.8 1009.90  4975.4 1005.85  5012.1 1004.03  5012.5 1003.53  5017.6 1004.03
  5043.9 1008.15  5121.8 1009.20  5212.2 1008.03  5375.8 1007.78  5410.8 1004.83
  5426.5 1005.82  5433.1 1010.31  5443.5 1014.40  5449.1 1013.57  5488.6 1016.86
  5522.3 1017.28  5539.3 1019.23  5544.9 1018.64  5584.5 1021.60  5688.8 1025.58
#Mann=5,-1,0
  4606.4    0.05       0  5012.1    0.05       0  5017.6    0.05       0
  5043.9    0.12       0  5212.2    0.05       0
Bank Sta=5012.1,5017.6
Exp/Cntr=0.3,0.1

Type RM Length L Ch R = 1,10140,479,479,479
BEGIN DESCRIPTION:
HARRIS BRANCH 18.0
END DESCRIPTION:
XS GIS Cut Line= 3
      2859955.64     10256053.10      2859762.75     10256001.00
      2858955.73     10256053.11
#Sta/Elev= 30
  4800.2 1017.88  4831.2 1016.27  4892.1 1007.81  4897.3 1009.08  4903.7 1007.17
  4914.1 1006.06  4965.9 1003.06  5007.1 1002.11  5014.4 1001.28  5014.8 1000.78
  5019.9 1001.28  5057.2 1005.73  5127.3 1005.72  5167.4 1004.33  5177.4 1002.88
  5207.5 1001.78  5217.5 1004.57  5227.5 1005.65  5264.1 1006.74  5347.8 1007.22
  5407.9 1011.28  5448.0 1012.08  5508.1 1016.02  5574.6 1016.69  5579.6 1015.91
  5618.4 1015.81  5698.5 1022.02  5727.4 1023.14  5732.4 1022.63  5808.7 1025.77
#Mann=3,-1,0
  4800.2    0.05       0  5014.4    0.03       0  5019.9    0.05       0
Bank Sta=5014.4,5019.9
Exp/Cntr=0.3,0.1

Type RM Length L Ch R = 1,9661,491,491,491
BEGIN DESCRIPTION:
HARRIS BRANCH 17.0
END DESCRIPTION:
XS GIS Cut Line= 3
      2860005.70     10255703.12      2859812.75     10255551.00
      2859405.66     10255653.12
#Sta/Elev= 30
  4754.3 1013.40  4757.5 1013.40  4761.5 1012.35  4782.3 1011.93  4860.9 1007.67
  4889.8 1005.16  4896.2 1005.43  4925.1 1003.60  4939.5 1004.20  4968.4  999.38
  4974.8  999.92  4982.8  996.50  4991.1  994.93  4991.6  994.43  4998.8  994.93
  5026.0  999.17  5031.1  998.73  5038.2  999.89  5048.5 1000.14  5089.8  999.67
  5100.1  997.03  5103.6  997.04  5135.0  997.23  5172.2  998.94  5190.7 1001.62
  5213.5 1002.09  5231.8 1003.55  5254.7 1004.11  5309.4 1007.05  5419.7 1012.48
#Mann=6,-1,0
  4754.3    0.05       0  4991.1    0.05       0  4998.8    0.05       0
  5103.6    0.12       0  5135.0    0.05       0  5309.4    0.12       0
Bank Sta=4991.1,4998.8
Exp/Cntr=0.3,0.1

Type RM Length L Ch R = 1,9170,407,407,407
BEGIN DESCRIPTION:
HARRIS BRANCH 16.0
END DESCRIPTION:
XS GIS Cut Line= 3
      2860205.73     10255203.13      2859892.25     10255072.00
      2859555.69     10255253.11
#Sta/Elev= 30
  4660.2 1009.85  4714.4 1007.17  4722.4 1006.35  4799.3 1002.03  4881.5  998.89
  4905.3  997.50  4920.4  997.71  4934.5  997.25  4952.9  993.63  4974.6  993.83
  4982.1  994.45  4987.5  994.12  4991.5  992.43  4992.0  991.93  4998.8  991.93
  4999.3  992.43  5007.3  992.97  5013.0  992.75  5018.8  993.82  5029.2  996.83
  5034.9  995.50  5041.5  997.96  5051.2  999.05  5116.9 1002.44  5122.6 1002.08
  5138.8 1003.22  5160.7 1003.31  5220.7 1005.51  5330.3 1007.08  5382.2 1009.08
#Mann=3,-1,0
  4660.2    0.05       0  4991.5    0.05       0  4999.3    0.05       0
Bank Sta=4991.5,4999.3
Exp/Cntr=0.3,0.1

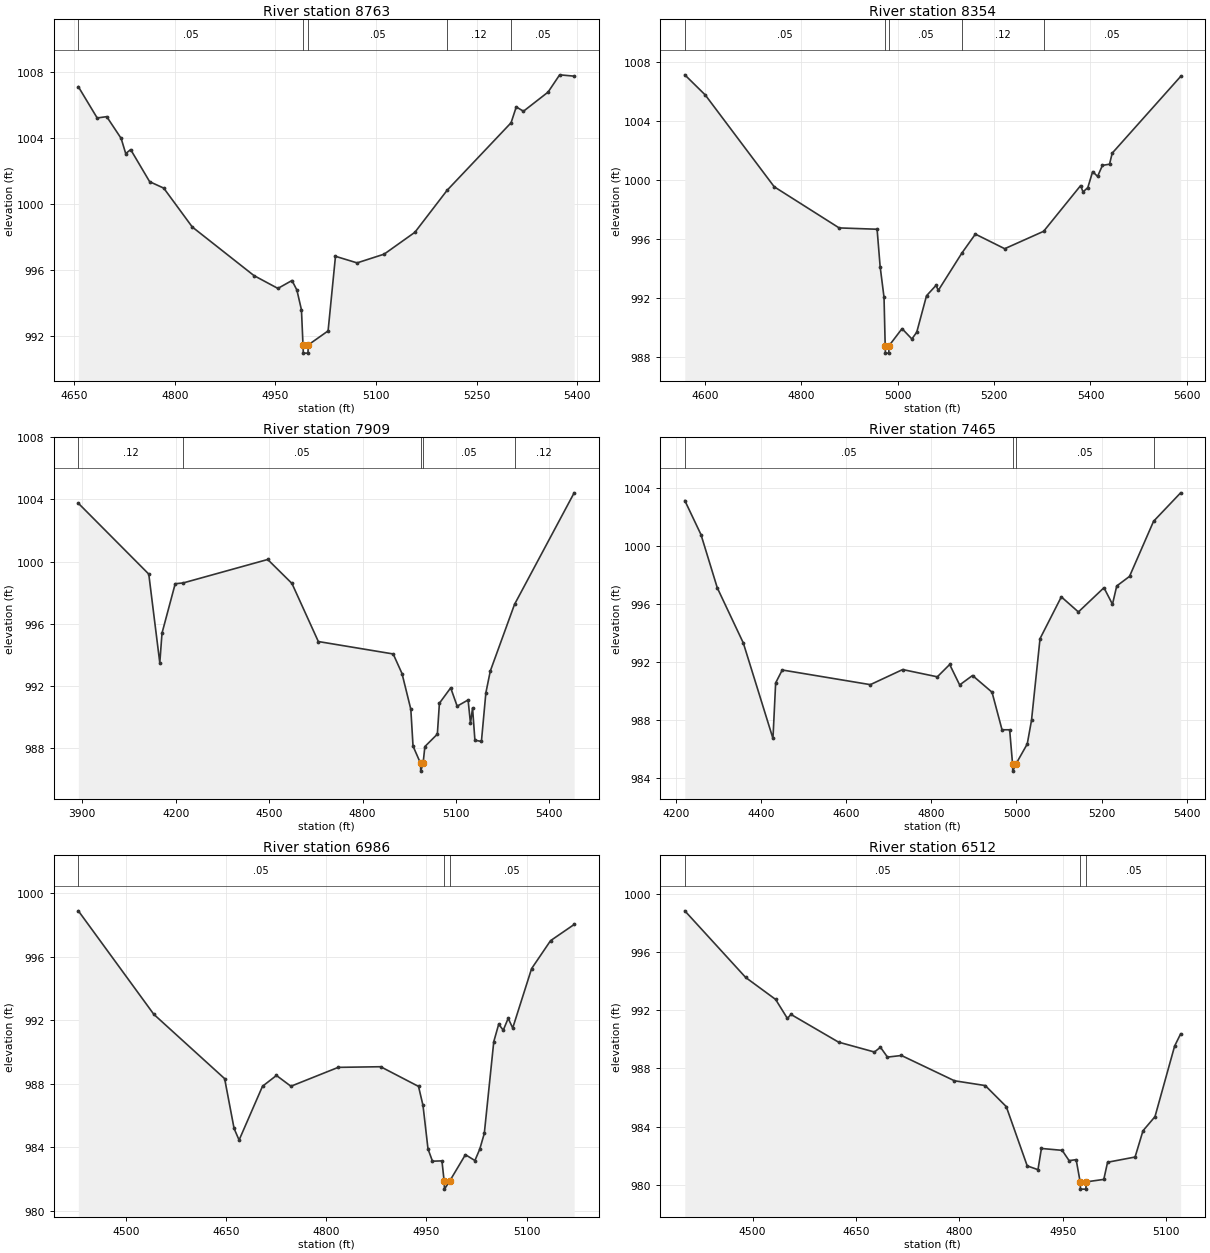
Type RM Length L Ch R = 1,8763,409,409,409
BEGIN DESCRIPTION:
HARRIS BRANCH 15.0
END DESCRIPTION:
XS GIS Cut Line= 3
      2860355.69     10255003.12      2860122.25     10254751.00
      2859755.66     10254603.10
#Sta/Elev= 30
  4656.4 1007.13  4684.5 1005.23  4698.7 1005.31  4720.2 1003.99  4727.0 1003.07
  4734.4 1003.31  4762.7 1001.36  4783.7 1000.97  4826.2  998.61  4918.1  995.66
  4953.8  994.88  4974.8  995.36  4982.1  994.78  4988.9  993.58  4991.2  991.45
  4991.7  990.95  4998.6  990.95  4999.1  991.45  5028.6  992.30  5039.6  996.83
  5071.8  996.43  5112.1  996.96  5158.0  998.29  5206.0 1000.84  5301.3 1004.94
  5309.0 1005.90  5319.8 1005.64  5356.4 1006.80  5373.7 1007.85  5395.3 1007.77
#Mann=5,-1,0
  4656.4    0.05       0  4991.2    0.05       0  4999.1    0.05       0
  5206.0    0.12       0  5301.3    0.05       0
Bank Sta=4991.2,4999.1
Exp/Cntr=0.3,0.1

Type RM Length L Ch R = 1,8354,445,445,445
BEGIN DESCRIPTION:
HARRIS BRANCH 14.0
END DESCRIPTION:
XS GIS Cut Line= 3
      2860655.71     10254803.14      2860384.50     10254454.00
      2859805.72     10254553.10
#Sta/Elev= 30
  4557.9 1007.16  4600.5 1005.79  4743.5  999.57  4878.3  996.78  4957.1  996.69
  4963.4  994.16  4971.5  992.07  4973.9  988.79  4974.4  988.29  4981.3  988.29
  4981.8  988.79  5008.9  989.95  5029.3  989.25  5039.4  989.71  5059.7  992.18
  5079.3  992.88  5084.3  992.55  5133.0  995.07  5161.1  996.36  5222.0  995.37
  5302.8  996.55  5379.6  999.65  5384.6  999.22  5394.5  999.51  5404.6 1000.60
  5414.8 1000.27  5424.9 1001.02  5439.6 1001.10  5445.2 1001.85  5587.2 1007.05
#Mann=5,-1,0
  4557.9    0.05       0  4973.9    0.03       0  4981.8    0.05       0
  5133.0    0.12       0  5302.8    0.05       0
Bank Sta=4973.9,4981.8
Exp/Cntr=0.3,0.1

Type RM Length L Ch R = 1,7909,444,444,444
BEGIN DESCRIPTION:
HARRIS BRANCH 13.0
END DESCRIPTION:
XS GIS Cut Line= 3
      2861155.65     10254803.08      2860369.00     10254016.00
      2860055.70     10253653.14
#Sta/Elev= 30
  3887.2 1003.75  4113.4  999.19  4148.8  993.48  4155.9  995.39  4198.3  998.57
  4223.7  998.62  4495.3 1000.13  4573.1  998.59  4657.9  994.85  4898.3  994.05
  4926.6  992.79  4954.9  990.49  4962.0  988.12  4986.2  987.01  4986.7  986.51
  4994.3  987.01  5000.0  988.09  5040.1  988.89  5046.7  990.88  5082.9  991.87
  5103.7  990.69  5138.8  991.09  5146.5  989.58  5153.1  990.58  5160.7  988.50
  5181.6  988.42  5195.9  991.55  5210.1  992.95  5287.9  997.24  5479.4 1004.42
#Mann=5,-1,0
  3887.2    0.12       0  4223.7    0.05       0  4986.2    0.05       0
  4994.3    0.05       0  5287.9    0.12       0
Bank Sta=4986.2,4994.3
Exp/Cntr=0.3,0.1

Type RM Length L Ch R = 1,7465,479,479,479
BEGIN DESCRIPTION:
HARRIS BRANCH 12.0
END DESCRIPTION:
XS GIS Cut Line= 3
      2861205.71     10253903.12      2860491.00     10253594.00
      2860105.71     10253603.11
#Sta/Elev= 30
  4221.3 1003.14  4259.3 1000.79  4297.6  997.12  4358.7  993.32  4428.3  986.74
  4434.6  990.57  4450.1  991.46  4656.9  990.45  4732.8  991.49  4814.2  990.99
  4843.2  991.84  4866.6  990.43  4896.8  991.08  4942.6  989.93  4966.1  987.34
  4984.0  987.34  4990.8  984.99  4991.3  984.49  4998.9  984.99  5025.3  986.36
  5035.3  987.99  5055.3  993.62  5105.3  996.50  5145.4  995.46  5205.4  997.13
  5225.4  995.99  5235.4  997.25  5265.4  997.91  5321.9 1001.71  5385.4 1003.67
#Mann=4,-1,0
  4221.3    0.05       0  4990.8    0.05       0  4998.9    0.05       0
  5321.9    0.12       0
Bank Sta=4990.8,4998.9
Exp/Cntr=0.3,0.1

Type RM Length L Ch R = 1,6986,474,474,474
BEGIN DESCRIPTION:
HARRIS BRANCH 11.0
END DESCRIPTION:
XS GIS Cut Line= 3
      2861255.68     10253753.10      2860872.00     10253329.00
      2860755.68     10253203.11
#Sta/Elev= 30
  4428.1  998.88  4541.3  992.36  4647.4  988.31  4661.6  985.17  4669.1  984.44
  4704.2  987.83  4725.1  988.51  4746.8  987.83  4817.7  989.02  4881.3  989.06
  4938.1  987.82  4944.8  986.62  4952.3  983.88  4959.0  983.11  4973.2  983.13
  4976.5  981.85  4977.0  981.35  4984.7  981.85  5008.4  983.52  5022.6  983.15
  5029.9  983.87  5036.7  984.86  5050.9  990.64  5058.3  991.74  5065.1  991.36
  5072.5  992.11  5079.3  991.50  5107.6  995.24  5136.0  997.00  5171.4  998.02
#Mann=3,-1,0
  4428.1    0.05       0  4976.5    0.03       0  4984.7    0.05       0
Bank Sta=4976.5,4984.7
Exp/Cntr=0.3,0.1

Type RM Length L Ch R = 1,6512,449,449,449
BEGIN DESCRIPTION:
HARRIS BRANCH 10.0
END DESCRIPTION:
XS GIS Cut Line= 3
      2861355.69     10253653.12      2861256.50     10253063.00
      2861205.67     10252953.08
#Sta/Elev= 30
  4401.6  998.85  4490.0  994.26  4533.4  992.75  4550.5  991.44  4555.6  991.72
  4624.7  989.81  4676.8  989.13  4685.5  989.46  4695.7  988.78  4716.0  988.89
  4792.9  987.15  4837.6  986.82  4868.1  985.37  4898.5  981.29  4914.1  981.03
  4919.1  982.49  4949.2  982.36  4959.3  981.65  4969.5  981.72  4975.3  980.19
  4975.8  979.69  4983.6  979.69  4984.1  980.19  5009.6  980.36  5015.1  981.54
  5055.0  981.90  5066.5  983.71  5083.9  984.68  5112.4  989.54  5121.1  990.38
#Mann=3,-1,0
  4401.6    0.05       0  4975.3    0.03       0  4984.1    0.05       0
Bank Sta=4975.3,4984.1
Exp/Cntr=0.3,0.1

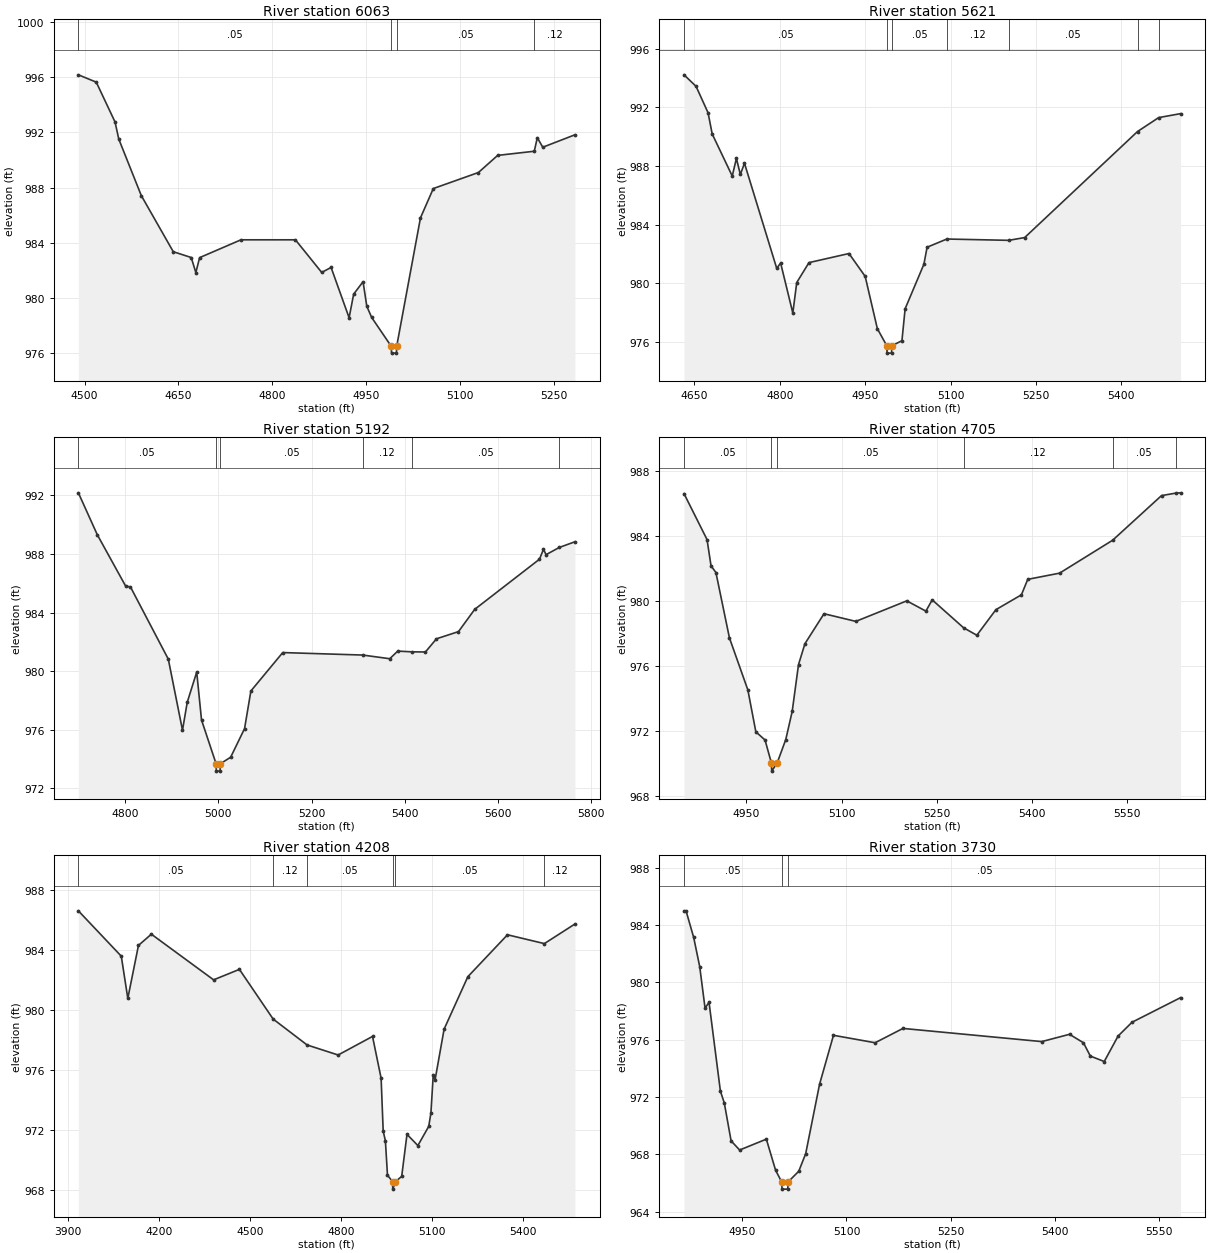
Type RM Length L Ch R = 1,6063,442,442,442
BEGIN DESCRIPTION:
HARRIS BRANCH 9.0
END DESCRIPTION:
XS GIS Cut Line= 3
      2861955.70     10253003.12      2861531.50     10252720.00
      2861255.69     10252653.11
#Sta/Elev= 30
  4490.0  996.16  4518.6  995.63  4548.6  992.75  4554.6  991.51  4590.6  987.42
  4641.7  983.36  4670.4  982.94  4677.8  981.85  4683.8  982.93  4749.9  984.22
  4837.0  984.22  4879.0  981.86  4894.0  982.22  4922.8  978.58  4930.1  980.29
  4945.1  981.19  4951.1  979.41  4958.9  978.60  4990.1  976.52  4990.6  976.02
  4998.4  976.02  4998.9  976.52  5036.9  985.81  5057.4  987.93  5129.5  989.09
  5160.3  990.33  5218.8  990.63  5223.7  991.61  5232.4  990.92  5283.8  991.82
#Mann=4,-1,0
  4490.0    0.05       0  4990.1    0.05       0  4998.9    0.05       0
  5218.8    0.12       0
Bank Sta=4990.1,4998.9
Exp/Cntr=0.3,0.1

Type RM Length L Ch R = 1,5621,429,429,429
BEGIN DESCRIPTION:
HARRIS BRANCH 8.0
END DESCRIPTION:
XS GIS Cut Line= 3
      2862155.65     10252803.08      2861903.25     10252535.00
      2861455.66     10252303.10
#Sta/Elev= 30
  4631.8  994.22  4653.0  993.43  4674.0  991.63  4681.3  990.18  4716.5  987.31
  4723.8  988.51  4730.7  987.42  4738.0  988.18  4794.6  981.01  4801.5  981.37
  4822.9  977.96  4829.8  980.04  4851.3  981.40  4921.6  982.02  4950.0  980.46
  4971.4  976.89  4988.0  975.72  4988.5  975.22  4996.3  975.22  4996.8  975.72
  5014.6  976.07  5020.2  978.25  5053.2  981.29  5058.8  982.45  5093.5  983.01
  5202.3  982.92  5230.2  983.11  5428.5  990.35  5465.6  991.30  5504.1  991.57
#Mann=7,-1,0
  4631.8    0.05       0  4988.0    0.03       0  4996.8    0.05       0
  5093.5    0.12       0  5202.3    0.05       0  5428.5    0.12       0
  5465.6    0.05       0
Bank Sta=4988,4996.8
Exp/Cntr=0.3,0.1

Type RM Length L Ch R = 1,5192,487,487,487
BEGIN DESCRIPTION:
HARRIS BRANCH 7.0
END DESCRIPTION:
XS GIS Cut Line= 3
      2862605.64     10252503.10      2862310.00     10252451.00
      2861605.70     10252153.12
#Sta/Elev= 30
  4699.8  992.17  4740.4  989.31  4801.3  985.80  4811.5  985.75  4892.7  980.82
  4923.1  975.97  4933.3  977.88  4953.6  979.94  4963.9  976.67  4995.2  973.68
  4995.7  973.18  5003.7  973.18  5004.2  973.68  5026.4  974.13  5056.2  976.08
  5069.8  978.65  5138.1  981.27  5309.7  981.10  5367.6  980.85  5384.7  981.37
  5415.0  981.32  5444.1  981.31  5467.8  982.21  5515.0  982.70  5549.8  984.22
  5688.7  987.64  5697.3  988.32  5702.8  987.95  5731.0  988.44  5764.7  988.83
#Mann=6,-1,0
  4699.8    0.05       0  4995.2    0.03       0  5004.2    0.05       0
  5309.7    0.12       0  5415.0    0.05       0  5731.0    0.12       0
Bank Sta=4995.2,5004.2
Exp/Cntr=0.3,0.1

Type RM Length L Ch R = 1,4705,497,497,497
BEGIN DESCRIPTION:
HARRIS BRANCH 6.0
END DESCRIPTION:
XS GIS Cut Line= 3
      2862705.67     10252153.10      2862587.75     10252063.00
      2861955.68     10252003.11
#Sta/Elev= 30
  4851.6  986.58  4887.9  983.76  4894.2  982.15  4901.9  981.74  4923.2  977.73
  4952.3  974.53  4964.9  971.96  4979.4  971.46  4989.4  970.05  4989.9  969.55
  4998.5  970.05  5012.1  971.49  5022.2  973.21  5032.2  976.09  5042.3  977.37
  5072.4  979.21  5122.6  978.74  5203.0  980.00  5233.1  979.37  5243.1  980.06
  5292.5  978.35  5313.5  977.89  5343.6  979.46  5383.8  980.37  5393.8  981.32
  5444.0  981.70  5527.7  983.72  5604.8  986.46  5627.1  986.61  5634.9  986.63
#Mann=6,-1,0
  4851.6    0.05       0  4989.4    0.03       0  4998.5    0.05       0
  5292.5    0.12       0  5527.7    0.05       0  5627.1    0.12       0
Bank Sta=4989.4,4998.5
Exp/Cntr=0.3,0.1

Type RM Length L Ch R = 1,4208,478,478,478
BEGIN DESCRIPTION:
HARRIS BRANCH 5.0
END DESCRIPTION:
XS GIS Cut Line= 3
      2863255.69     10252353.12      2862524.75     10251578.00
      2862055.70     10251903.10
#Sta/Elev= 30
  3934.6  986.63  4076.0  983.60  4097.5  980.78  4132.6  984.32  4175.1  985.07
  4380.2  982.02  4465.2  982.72  4576.4  979.40  4688.2  977.67  4790.5  977.00
  4903.8  978.24  4932.1  975.45  4939.0  971.91  4946.2  971.27  4953.1  968.97
  4970.0  968.54  4970.5  968.04  4979.2  968.54  4999.9  968.89  5017.4  971.70
  5053.2  970.95  5089.0  972.23  5096.2  973.12  5103.9  975.68  5110.0  975.35
  5139.7  978.73  5217.9  982.23  5348.5  985.03  5470.0  984.44  5570.7  985.75
#Mann=6,-1,0
  3934.6    0.05       0  4576.4    0.12       0  4688.2    0.05       0
  4970.0    0.03       0  4979.2    0.05       0  5470.0    0.12       0
Bank Sta=4970,4979.2
Exp/Cntr=0.3,0.1

Type RM Length L Ch R = 1,3730,492,492,492
BEGIN DESCRIPTION:
HARRIS BRANCH 4.0
END DESCRIPTION:
XS GIS Cut Line= 3
      2862905.72     10251303.13      2862787.00     10251241.00
      2862205.73     10251253.11
#Sta/Elev= 30
  4866.0  985.00  4868.9  985.00  4879.9  983.14  4888.6  981.10  4896.3  978.20
  4902.0  978.62  4918.4  972.41  4924.0  971.59  4933.8  968.94  4946.1  968.30
  4984.6  969.06  4997.9  966.89  5006.7  966.07  5007.2  965.57  5015.4  965.57
  5015.9  966.07  5031.3  966.82  5041.3  968.05  5061.3  972.90  5081.3  976.31
  5141.3  975.79  5181.4  976.79  5381.4  975.87  5421.4  976.38  5441.4  975.79
  5451.4  974.86  5471.4  974.48  5491.4  976.26  5511.4  977.22  5581.4  978.94
#Mann=3,-1,0
  4866.0    0.05       0  5006.7    0.05       0  5015.9    0.05       0
Bank Sta=5006.7,5015.9
Exp/Cntr=0.3,0.1

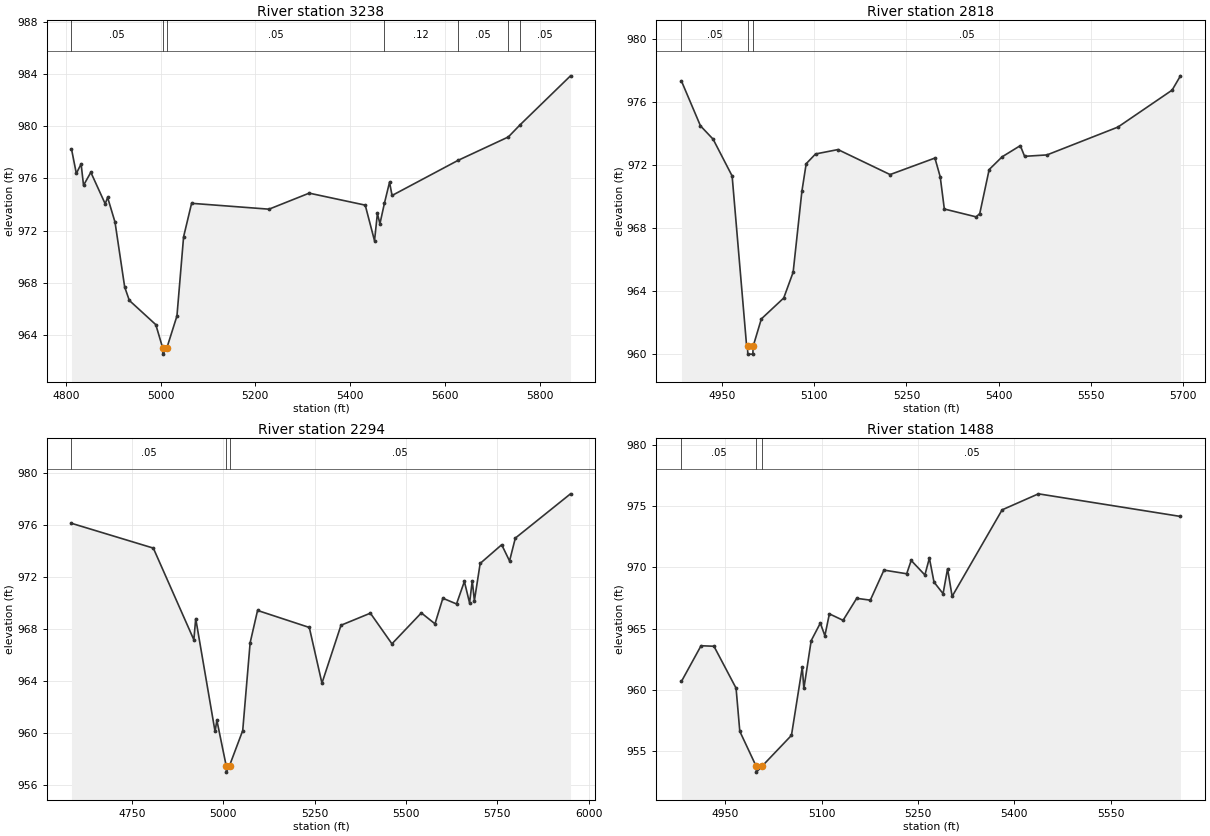
Type RM Length L Ch R = 1,3238,420,420,420
BEGIN DESCRIPTION:
HARRIS BRANCH 3.0
END DESCRIPTION:
XS GIS Cut Line= 3
      2862955.70     10250853.11      2862771.50     10250816.00
      2861955.65     10251103.12
#Sta/Elev= 30
  4812.1  978.26  4822.3  976.38  4832.4  977.11  4837.5  975.47  4852.9  976.47
  4883.2  974.05  4888.3  974.54  4903.9  972.65  4924.3  967.67  4934.1  966.64
  4990.0  964.78  5004.3  963.02  5004.8  962.52  5013.5  963.02  5034.6  965.45
  5048.6  971.52  5065.5  974.09  5228.8  973.64  5313.6  974.87  5431.8  973.95
  5451.4  971.22  5457.5  973.31  5462.8  972.52  5472.4  974.11  5483.1  975.71
  5488.4  974.69  5627.4  977.38  5733.7  979.18  5758.5  980.11  5864.9  983.87
#Mann=7,-1,0
  4812.1    0.05       0  5004.3    0.05       0  5013.5    0.05       0
  5472.4    0.12       0  5627.4    0.05       0  5733.7    0.12       0
  5758.5    0.05       0
Bank Sta=5004.3,5013.5
Exp/Cntr=0.3,0.1

Type RM Length L Ch R = 1,2818,524,524,524
BEGIN DESCRIPTION:
HARRIS BRANCH 2.0
END DESCRIPTION:
XS GIS Cut Line= 3
      2862755.64     10250403.12      2862643.25     10250431.00
      2862055.67     10250803.12
#Sta/Elev= 30
  4884.2  977.34  4915.1  974.49  4935.7  973.64  4966.6  971.30  4990.2  960.47
  4991.6  960.47  4992.1  959.97  5000.3  959.97  5000.8  960.47  5014.1  962.21
  5050.5  963.54  5065.8  965.18  5080.0  970.32  5087.0  972.08  5102.2  972.70
  5138.7  972.98  5223.4  971.39  5296.3  972.44  5304.9  971.25  5311.6  969.20
  5363.3  968.70  5369.2  968.91  5384.5  971.71  5405.6  972.52  5435.1  973.23
  5442.1  972.55  5478.5  972.64  5593.8  974.41  5681.9  976.76  5695.5  977.67
#Mann=3,-1,0
  4884.2    0.05       0  4991.6    0.03       0  5000.8    0.05       0
Bank Sta=4991.6,5000.8
Exp/Cntr=0.3,0.1

Type RM Length L Ch R = 1,2294,806,806,806
BEGIN DESCRIPTION:
Mapping XS a78f2e06
END DESCRIPTION:
XS GIS Cut Line= 3
      2862806.31     10250059.73      2862243.78     10249955.56
      2861556.28     10250351.39
#Sta/Elev= 30
  4584.9  976.13  4808.8  974.22  4919.7  967.16  4924.8  968.79  4977.7  960.10
  4982.7  960.96  5008.1  957.47  5008.6  956.97  5017.3  957.47  5053.4  960.17
  5073.7  966.93  5094.0  969.42  5235.6  968.11  5270.2  963.82  5322.3  968.28
  5402.7  969.21  5461.7  966.85  5542.1  969.23  5579.5  968.39  5601.0  970.36
  5638.4  969.92  5659.9  971.65  5674.1  970.00  5681.5  971.70  5687.3  970.17
  5703.1  973.04  5762.0  974.48  5783.5  973.23  5799.3  974.99  5950.3  978.40
#Mann=3,-1,0
  4584.9    0.05       0  5008.1    0.03       0  5017.3    0.05       0
Bank Sta=5008.1,5017.3
Exp/Cntr=0.3,0.1

Type RM Length L Ch R = 1,1488,0,0,0
BEGIN DESCRIPTION:
HARRIS BRANCH 1.0
END DESCRIPTION:
XS GIS Cut Line= 3
      2862456.09     10249266.08      2862265.70     10249247.97
      2861856.16     10249666.06
#Sta/Elev= 30
  4881.9  960.67  4912.4  963.59  4932.5  963.55  4966.9  960.12  4972.7  956.59
  4998.0  953.75  4998.5  953.25  5007.6  953.75  5053.1  956.26  5069.9  961.84
  5072.4  960.10  5083.8  964.01  5098.0  965.44  5105.1  964.41  5112.1  966.20
  5133.4  965.67  5154.6  967.47  5175.8  967.32  5197.0  969.78  5232.4  969.48
  5239.4  970.57  5260.7  969.38  5267.7  970.76  5274.9  968.80  5289.0  967.85
  5296.0  969.89  5303.1  967.63  5380.9  974.71  5437.4  976.02  5658.4  974.17
#Mann=3,-1,0
  4881.9    0.05       0  4998.0    0.03       0  5007.6    0.05       0
Bank Sta=4998,5007.6
Exp/Cntr=0.3,0.1

Chan Stop Cuts=-1