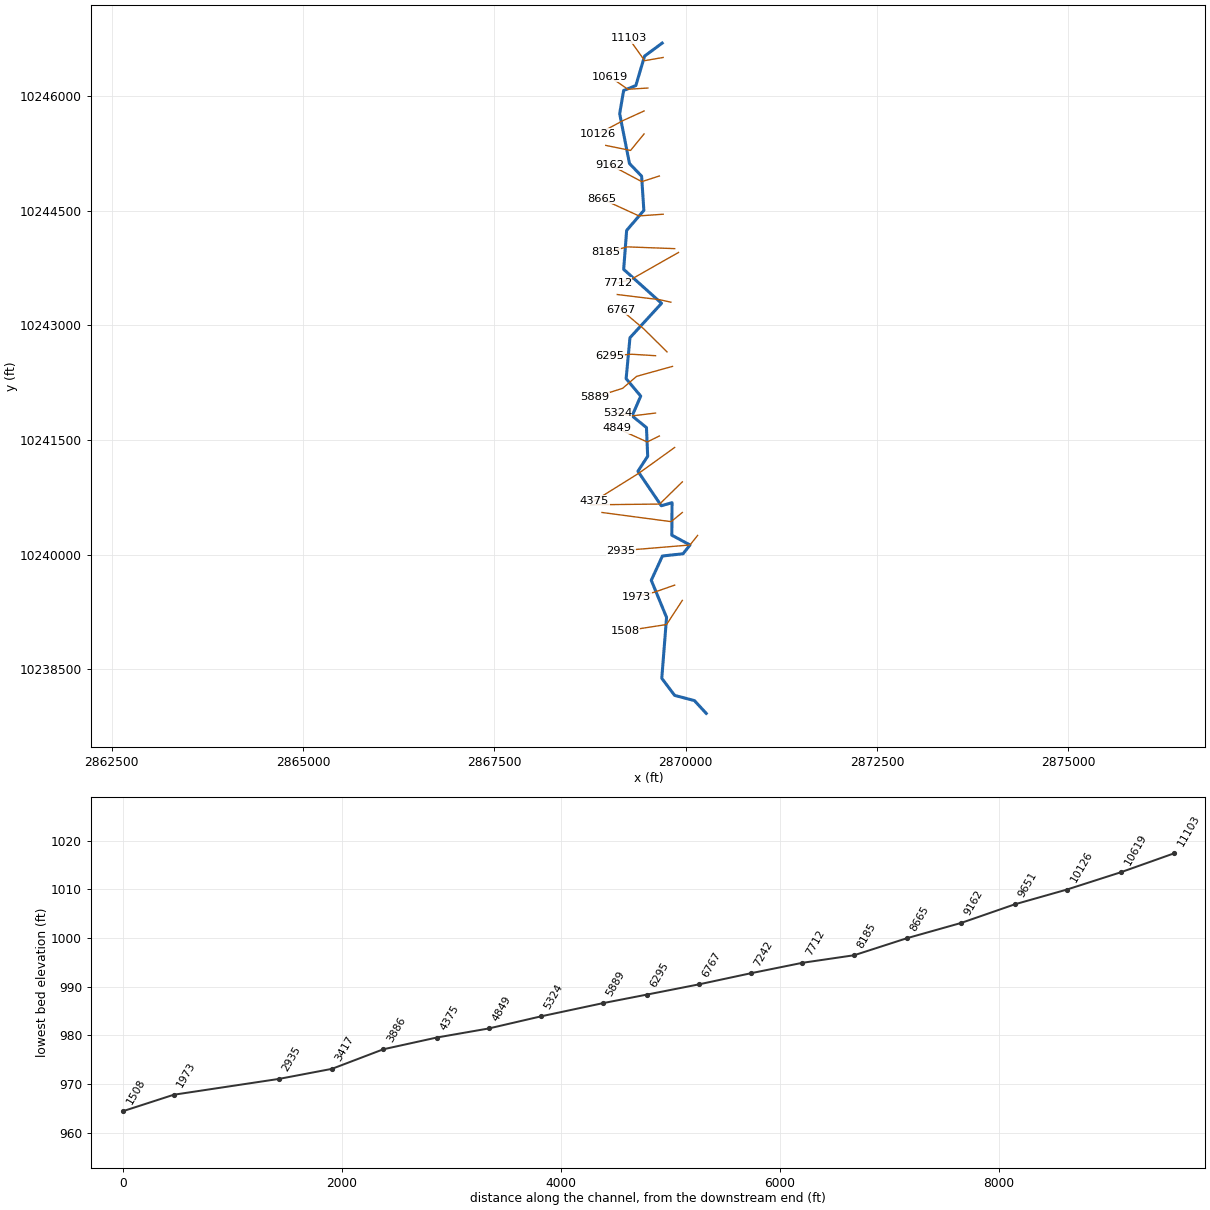
--- LITTLE LLANO 006.prj (project) ---

Proj Title=LITTLE LLANO 006 Base Level Engineering
Current Plan=p01
Default Exp/Contr=0.3,0.1
English Units
Geom File=g01
Flow File=f01
Plan File=p01
BEGIN DESCRIPTION:
LITTLE LLANO 006
END DESCRIPTION:

--- LITTLE LLANO 006.p01 (plan) ---

Plan Title=Multiple Run
Short Identifier=Multiple
Geom File=g01
Flow File=f01
Subcritical Flow
K Sum by GR= 0
Std Step Tol= 0.01
Critical Tol= 0.01
Num of Std Step Trials= 20
Max Error Tol= 0.3
Flow Tol Ratio= 0.001
Split Flow NTrial= 30
Split Flow Tol= 0.02
Split Flow Ratio= 0.02
Log Output Level= 0
Friction Slope Method= 1
Unsteady Friction Slope Method= 2
Unsteady Bridges Friction Slope Method= 1
Parabolic Critical Depth
Global Vel Dist=  1 , 1 , 1
Global Log Level= 0
CheckData=True
Encroach Param= -1, 0, 0, 0
BEGIN DESCRIPTION:
Multiple Run
END DESCRIPTION:

--- LITTLE LLANO 006.f01 (steady flow) ---

Flow Title=Multiple
Number of Profiles=7
Profile Names=10-year,25-year,50-year,1pct_min,100-year,1pct_plu,500-year
River Rch & RM= LITTLE LLANO 006,Reach-1,11103
      63     121     190      99     298     899     783
Boundary for River Rch & Prof#=LITTLE LLANO 006,Reach-1,1
Up Type=0
Dn Type=3
Dn Slope=0.005
Boundary for River Rch & Prof#=LITTLE LLANO 006,Reach-1,2
Up Type=0
Dn Type=3
Dn Slope=0.005
Boundary for River Rch & Prof#=LITTLE LLANO 006,Reach-1,3
Up Type=0
Dn Type=3
Dn Slope=0.005
Boundary for River Rch & Prof#=LITTLE LLANO 006,Reach-1,4
Up Type=0
Dn Type=3
Dn Slope=0.005
Boundary for River Rch & Prof#=LITTLE LLANO 006,Reach-1,5
Up Type=0
Dn Type=3
Dn Slope=0.005
Boundary for River Rch & Prof#=LITTLE LLANO 006,Reach-1,6
Up Type=0
Dn Type=3
Dn Slope=0.005
Boundary for River Rch & Prof#=LITTLE LLANO 006,Reach-1,7
Up Type=0
Dn Type=3
Dn Slope=0.005

--- LITTLE LLANO 006.g01 (geometry) ---

Geom Title=Existing Conditions

River Reach=LITTLE LLANO 006,Reach-1
Reach XY= 30
      2869693.00     10246691.00      2869462.50     10246521.00
      2869348.50     10246136.00      2869189.00     10246071.00
      2869137.00     10245768.00      2869265.25     10245116.00
      2869423.75     10244951.00      2869453.00     10244503.00
      2869228.00     10244241.00      2869189.50     10243732.00
      2869684.25     10243288.00      2869271.50     10242838.00
      2869221.50     10242303.00      2869412.25     10242075.00
      2869299.75     10241816.00      2869487.25     10241663.00
      2869503.00     10241288.00      2869375.50     10241092.00
      2869681.00     10240641.00      2869821.50     10240681.00
      2869818.50     10240256.00      2870056.00     10240128.00
      2869965.25     10240013.00      2869695.75     10239984.00
      2869550.00     10239666.00      2869749.75     10239181.00
      2869687.25     10238384.00      2869855.50     10238161.00
      2870113.75     10238093.00      2870268.00     10237926.00

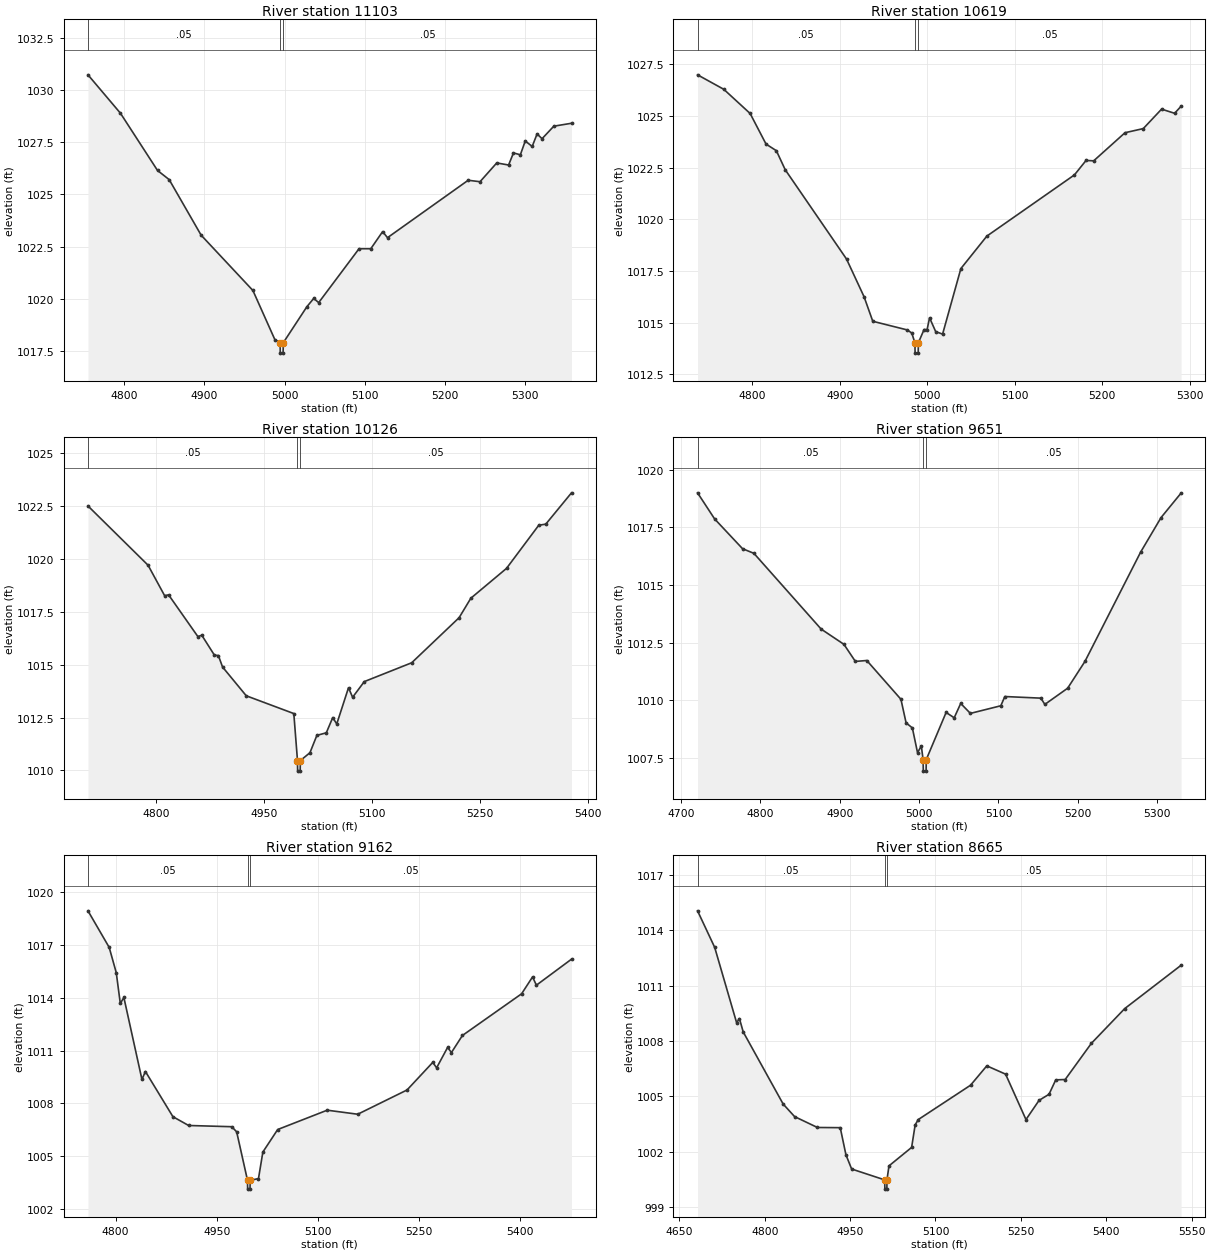
Type RM Length L Ch R = 1,11103,484,484,484
BEGIN DESCRIPTION:
LITTLE LLANO 006 20.0
END DESCRIPTION:
XS GIS Cut Line= 3
      2869705.71     10246503.12      2869463.75     10246461.00
      2869255.71     10246753.08
#Sta/Elev= 30
  4754.4 1030.73  4795.0 1028.89  4841.3 1026.15  4855.9 1025.71  4895.8 1023.05
  4960.5 1020.40  4987.9 1018.05  4994.5 1017.90  4994.7 1017.40  4998.2 1017.40
  4998.5 1017.90  5027.9 1019.62  5036.5 1020.02  5042.7 1019.82  5093.1 1022.40
  5107.8 1022.40  5122.6 1023.22  5128.7 1022.93  5229.5 1025.68  5244.3 1025.61
  5265.2 1026.51  5280.0 1026.41  5286.1 1026.99  5294.7 1026.90  5300.8 1027.56
  5309.5 1027.30  5315.6 1027.90  5321.8 1027.67  5336.5 1028.27  5358.6 1028.41
#Mann=3,-1,0
  4754.4    0.05       0  4994.5    0.05       0  4998.5    0.05       0
Bank Sta=4994.5,4998.5
Exp/Cntr=0.3,0.1

Type RM Length L Ch R = 1,10619,493,493,493
BEGIN DESCRIPTION:
LITTLE LLANO 006 19.0
END DESCRIPTION:
XS GIS Cut Line= 3
      2869505.66     10246103.11      2869243.75     10246087.00
      2869005.68     10246253.12
#Sta/Elev= 30
  4737.6 1026.99  4767.6 1026.29  4797.7 1025.12  4815.9 1023.64  4827.7 1023.32
  4837.8 1022.40  4907.9 1018.08  4927.9 1016.26  4937.9 1015.07  4977.5 1014.65
  4982.5 1014.50  4986.0 1014.03  4986.3 1013.53  4989.8 1013.53  4990.0 1014.03
  4996.5 1014.67  5000.0 1014.67  5002.8 1015.24  5009.8 1014.57  5017.7 1014.45
  5038.6 1017.62  5068.3 1019.19  5168.4 1022.15  5181.7 1022.85  5190.4 1022.83
  5226.2 1024.19  5247.1 1024.39  5268.0 1025.33  5282.9 1025.13  5290.3 1025.47
#Mann=3,-1,0
  4737.6    0.05       0  4986.0    0.03       0  4990.0    0.05       0
Bank Sta=4986,4990
Exp/Cntr=0.3,0.1

Type RM Length L Ch R = 1,10126,475,475,475
BEGIN DESCRIPTION:
LITTLE LLANO 006 18.0
END DESCRIPTION:
XS GIS Cut Line= 3
      2869455.64     10245803.09      2869187.75     10245681.00
      2868855.69     10245503.12
#Sta/Elev= 30
  4705.6 1022.50  4789.0 1019.70  4812.0 1018.26  4817.5 1018.30  4858.1 1016.33
  4863.6 1016.39  4881.1 1015.45  4886.6 1015.43  4892.4 1014.89  4925.3 1013.53
  4991.3 1012.69  4996.4 1010.47  4996.6 1009.97  5000.1 1009.97  5000.4 1010.47
  5013.7 1010.84  5023.3 1011.66  5036.4 1011.78  5045.3 1012.50  5050.9 1012.20
  5067.2 1013.91  5072.9 1013.46  5089.1 1014.20  5154.9 1015.09  5220.7 1017.22
  5237.0 1018.14  5286.5 1019.55  5331.3 1021.59  5341.0 1021.64  5376.7 1023.12
#Mann=3,-1,0
  4705.6    0.05       0  4996.4    0.05       0  5000.4    0.05       0
Bank Sta=4996.4,5000.4
Exp/Cntr=0.3,0.1

Type RM Length L Ch R = 1,9651,489,489,489
BEGIN DESCRIPTION:
LITTLE LLANO 006 17.0
END DESCRIPTION:
XS GIS Cut Line= 3
      2869455.66     10245503.08      2869279.00     10245287.00
      2868955.69     10245353.11
#Sta/Elev= 30
  4720.9 1018.99  4742.4 1017.86  4777.6 1016.57  4791.9 1016.37  4876.6 1013.09
  4905.3 1012.43  4919.7 1011.69  4934.1 1011.73  4977.1 1010.05  4983.6 1009.03
  4991.5 1008.81  4998.0 1007.74  5002.8 1008.03  5005.0 1007.44  5005.3 1006.94
  5008.8 1006.94  5009.0 1007.44  5034.0 1009.48  5044.2 1009.25  5052.4 1009.87
  5064.6 1009.44  5102.9 1009.77  5108.0 1010.17  5153.3 1010.10  5158.4 1009.83
  5187.1 1010.53  5208.9 1011.69  5279.0 1016.42  5304.8 1017.92  5330.0 1018.98
#Mann=3,-1,0
  4720.9    0.05       0  5005.0    0.05       0  5009.0    0.05       0
Bank Sta=5005,5009
Exp/Cntr=0.3,0.1

Type RM Length L Ch R = 1,9162,497,497,497
BEGIN DESCRIPTION:
LITTLE LLANO 006 16.0
END DESCRIPTION:
XS GIS Cut Line= 3
      2869655.68     10244953.11      2869426.25     10244879.00
      2869005.64     10245103.13
#Sta/Elev= 30
  4758.9 1018.95  4790.4 1016.87  4800.9 1015.43  4806.9 1013.68  4812.2 1014.02
  4839.0 1009.36  4844.2 1009.81  4885.0 1007.24  4908.3 1006.74  4972.3 1006.67
  4979.6 1006.38  4995.7 1003.62  4995.9 1003.12  4999.4 1003.12  4999.7 1003.62
  5012.0 1003.72  5018.5 1005.23  5040.5 1006.51  5114.0 1007.61  5159.3 1007.38
  5232.5 1008.76  5270.7 1010.33  5276.4 1010.02  5292.7 1011.18  5298.4 1010.89
  5314.7 1011.86  5402.5 1014.23  5418.8 1015.19  5424.5 1014.72  5476.6 1016.20
#Mann=3,-1,0
  4758.9    0.05       0  4995.7    0.03       0  4999.7    0.05       0
Bank Sta=4995.7,4999.7
Exp/Cntr=0.3,0.1

Type RM Length L Ch R = 1,8665,480,480,480
BEGIN DESCRIPTION:
LITTLE LLANO 006 15.0
END DESCRIPTION:
XS GIS Cut Line= 3
      2869705.73     10244453.11      2869388.50     10244431.00
      2868905.64     10244653.13
#Sta/Elev= 30
  4682.0 1015.05  4712.1 1013.07  4750.6 1008.99  4755.6 1009.21  4762.2 1008.49
  4832.4 1004.58  4852.5 1003.90  4892.6 1003.31  4932.7 1003.30  4942.7 1001.83
  4952.7 1001.06  5010.8 1000.47  5011.1  999.97  5014.6  999.97  5014.8 1000.47
  5018.3 1001.23  5058.1 1002.23  5064.3 1003.45  5069.8 1003.74  5161.6 1005.60
  5190.2 1006.65  5223.2 1006.20  5259.0 1003.74  5282.0 1004.78  5299.5 1005.11
  5311.3 1005.89  5327.9 1005.91  5373.9 1007.87  5432.4 1009.75  5531.5 1012.10
#Mann=3,-1,0
  4682.0    0.05       0  5010.8    0.03       0  5014.8    0.05       0
Bank Sta=5010.8,5014.8
Exp/Cntr=0.3,0.1

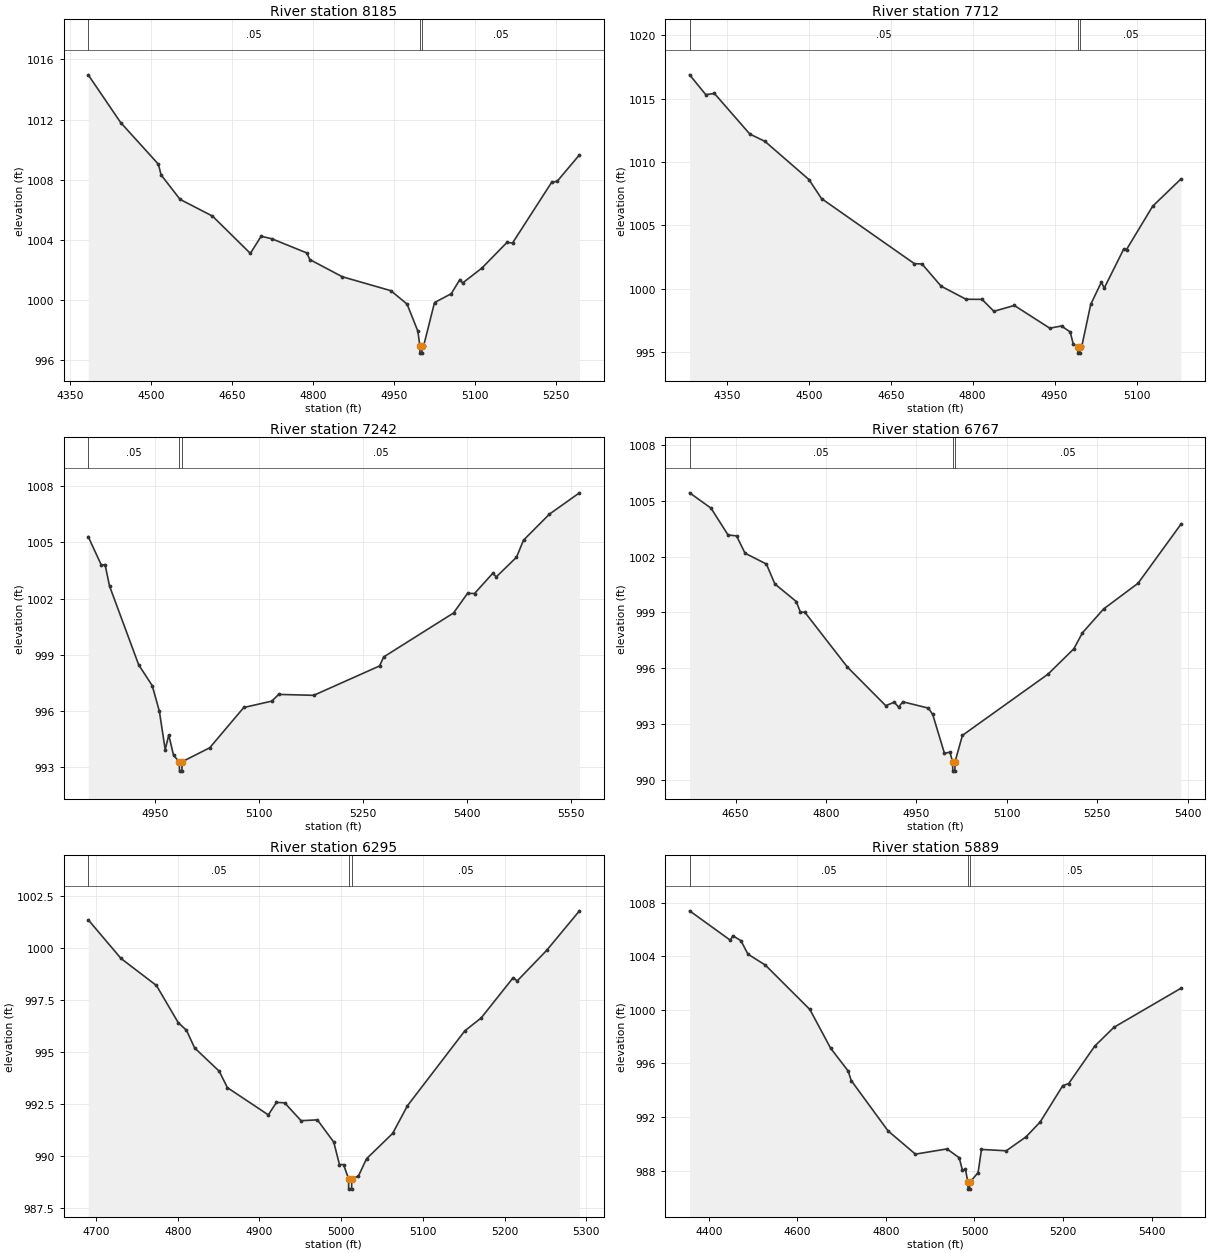
Type RM Length L Ch R = 1,8185,473,473,473
BEGIN DESCRIPTION:
LITTLE LLANO 006 14.0
END DESCRIPTION:
XS GIS Cut Line= 3
      2869855.68     10244003.11      2869239.50     10244026.00
      2868955.71     10243953.12
#Sta/Elev= 30
  4383.4 1014.98  4443.4 1011.81  4513.3 1009.04  4518.3 1008.33  4553.5 1006.70
  4613.5 1005.59  4683.6 1003.11  4703.6 1004.25  4723.6 1004.08  4788.1 1003.14
  4793.7 1002.70  4853.7 1001.56  4943.8 1000.63  4973.8  999.74  4993.8  997.94
  4997.4  996.98  4997.7  996.48  5001.2  996.48  5001.4  996.98  5004.6  996.98
  5024.6  999.84  5055.6 1000.43  5071.5 1001.37  5076.6 1001.14  5112.2 1002.13
  5158.8 1003.84  5169.1 1003.80  5241.4 1007.83  5251.7 1007.90  5293.0 1009.66
#Mann=3,-1,0
  4383.4    0.05       0  4997.4    0.03       0  5001.4    0.05       0
Bank Sta=4997.4,5001.4
Exp/Cntr=0.3,0.1

Type RM Length L Ch R = 1,7712,470,470,470
BEGIN DESCRIPTION:
LITTLE LLANO 006 13.0
END DESCRIPTION:
XS GIS Cut Line= 3
      2869905.64     10243953.09      2869281.25     10243598.00
      2869105.70     10243553.11
#Sta/Elev= 30
  4281.7 1016.87  4311.2 1015.31  4327.1 1015.40  4391.9 1012.20  4419.7 1011.62
  4500.2 1008.61  4523.2 1007.11  4693.2 1001.98  4707.3 1001.95  4742.2 1000.20
  4787.8  999.17  4817.2  999.16  4838.8  998.22  4876.3  998.68  4941.1  996.89
  4962.7  997.06  4978.6  996.59  4984.3  995.61  4992.5  995.42  4992.7  994.92
  4996.2  994.92  4996.5  995.42  4999.9  995.48  5016.1  998.76  5035.7 1000.52
  5040.9 1000.05  5076.6 1003.13  5081.7 1003.09  5129.6 1006.51  5181.2 1008.65
#Mann=3,-1,0
  4281.7    0.05       0  4992.5    0.05       0  4996.5    0.05       0
Bank Sta=4992.5,4996.5
Exp/Cntr=0.3,0.1

Type RM Length L Ch R = 1,7242,475,475,475
BEGIN DESCRIPTION:
LITTLE LLANO 006 12.0
END DESCRIPTION:
XS GIS Cut Line= 3
      2869805.67     10243303.12      2869663.50     10243335.00
      2869105.64     10243403.12
#Sta/Elev= 30
  4854.3 1005.31  4873.4 1003.77  4878.5 1003.82  4885.0 1002.67  4927.0  998.46
  4946.5  997.35  4956.8  995.98  4965.2  993.93  4970.3  994.71  4977.3  993.62
  4985.5  993.28  4985.8  992.78  4989.3  992.78  4989.5  993.28  5029.4  994.03
  5078.4  996.18  5118.7  996.52  5128.8  996.88  5179.1  996.83  5274.0  998.40
  5279.9  998.88  5380.6 1001.23  5400.8 1002.28  5410.8 1002.27  5437.1 1003.35
  5442.2 1003.16  5471.3 1004.21  5481.4 1005.12  5518.7 1006.51  5562.0 1007.65
#Mann=3,-1,0
  4854.3    0.05       0  4985.5    0.05       0  4989.5    0.05       0
Bank Sta=4985.5,4989.5
Exp/Cntr=0.3,0.1

Type RM Length L Ch R = 1,6767,472,472,472
BEGIN DESCRIPTION:
LITTLE LLANO 006 11.0
END DESCRIPTION:
XS GIS Cut Line= 3
      2869755.69     10242653.10      2869453.00     10242953.00
      2869155.70     10243203.09
#Sta/Elev= 30
  4573.9 1005.42  4609.3 1004.60  4637.6 1003.16  4651.7 1003.11  4665.8 1002.18
  4701.2 1001.60  4715.3 1000.53  4750.7  999.59  4757.7  999.01  4764.8  999.02
  4835.6  996.07  4899.2  994.00  4913.3  994.19  4920.4  993.92  4927.4  994.21
  4969.9  993.87  4977.0  993.53  4996.5  991.44  5005.5  991.51  5010.0  990.99
  5010.3  990.49  5013.8  990.49  5014.0  990.99  5026.3  992.41  5168.1  995.69
  5211.0  997.05  5225.3  997.91  5260.4  999.19  5317.6 1000.57  5388.5 1003.73
#Mann=3,-1,0
  4573.9    0.05       0  5010.0    0.03       0  5014.0    0.05       0
Bank Sta=5010,5014
Exp/Cntr=0.3,0.1

Type RM Length L Ch R = 1,6295,406,406,406
BEGIN DESCRIPTION:
LITTLE LLANO 006 10.0
END DESCRIPTION:
XS GIS Cut Line= 3
      2869605.67     10242603.11      2869296.75     10242622.00
      2869005.66     10242603.11
#Sta/Elev= 30
  4690.5 1001.35  4730.6  999.49  4774.0  998.19  4800.7  996.40  4810.7  996.04
  4820.7  995.19  4850.8  994.07  4860.8  993.28  4910.9  991.97  4920.9  992.57
  4930.9  992.55  4951.0  991.69  4971.0  991.73  4991.0  990.66  4998.0  989.58
  5003.0  989.58  5009.1  988.90  5009.3  988.40  5012.8  988.40  5013.1  988.90
  5021.1  989.02  5031.1  989.86  5063.1  991.08  5081.2  992.41  5151.4  996.01
  5171.4  996.63  5210.5  998.56  5215.5  998.41  5251.6  999.88  5291.7 1001.78
#Mann=3,-1,0
  4690.5    0.05       0  5009.1    0.03       0  5013.1    0.05       0
Bank Sta=5009.1,5013.1
Exp/Cntr=0.3,0.1

Type RM Length L Ch R = 1,5889,565,565,565
BEGIN DESCRIPTION:
Mapping XS 8853a58a
END DESCRIPTION:
XS GIS Cut Line= 4
      2869827.33     10242463.42      2869358.62     10242333.22
      2869176.33     10242176.97      2868811.75     10242059.79
#Sta/Elev= 30
  4356.7 1007.38  4448.9 1005.18  4454.1 1005.53  4472.6 1005.15  4488.4 1004.15
  4527.8 1003.33  4628.3 1000.02  4675.2  997.13  4714.6  995.44  4721.7  994.72
  4804.7  990.97  4866.6  989.23  4937.9  989.62  4965.6  988.96  4973.0  988.01
  4979.6  988.11  4985.3  987.12  4985.6  986.62  4989.1  986.62  4989.3  987.12
  5008.2  987.85  5015.9  989.58  5071.8  989.48  5116.5  990.52  5148.5  991.63
  5199.5  994.34  5212.7  994.49  5271.7  997.29  5315.0  998.69  5466.2 1001.60
#Mann=3,-1,0
  4356.7    0.05       0  4985.3    0.03       0  4989.3    0.05       0
Bank Sta=4985.3,4989.3
Exp/Cntr=0.3,0.1

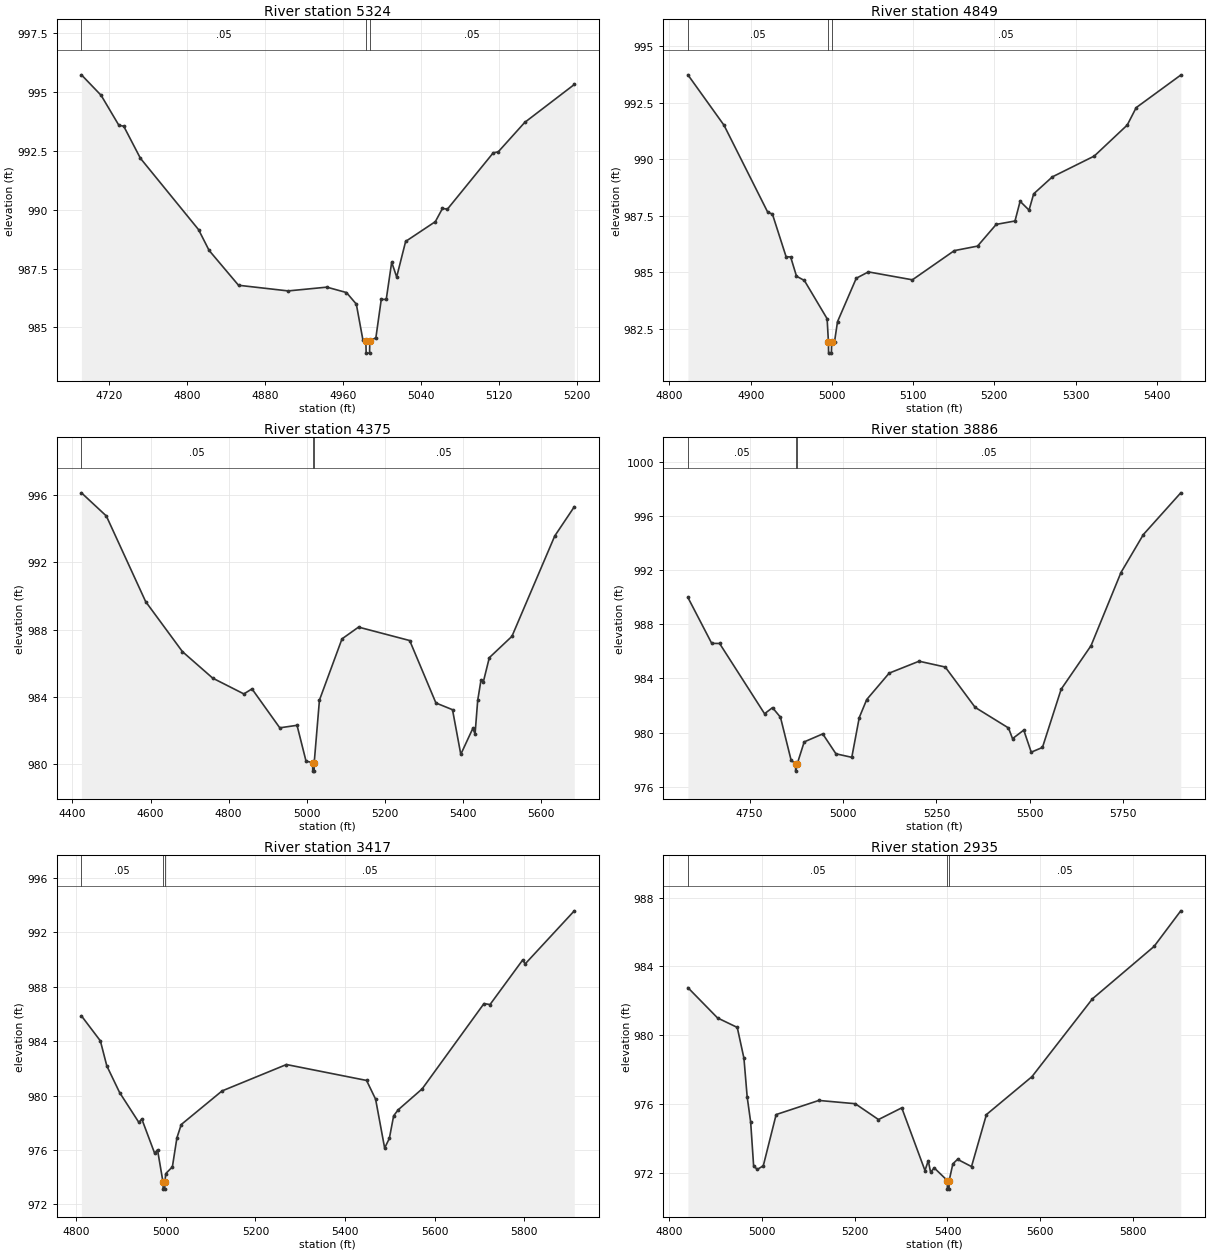
Type RM Length L Ch R = 1,5324,475,475,475
BEGIN DESCRIPTION:
LITTLE LLANO 006 8.0
END DESCRIPTION:
XS GIS Cut Line= 3
      2869605.71     10241853.11      2869299.75     10241816.00
      2869105.67     10241853.11
#Sta/Elev= 30
  4691.8  995.72  4712.0  994.85  4730.2  993.58  4735.2  993.54  4752.3  992.18
  4812.0  989.15  4822.8  988.27  4853.0  986.79  4903.9  986.55  4943.7  986.71
  4963.8  986.48  4973.9  985.99  4980.7  984.46  4983.7  984.41  4984.0  983.91
  4987.5  983.91  4987.7  984.41  4994.0  984.57  4999.5  986.19  5004.6  986.19
  5010.2  987.77  5015.3  987.14  5024.5  988.65  5055.0  989.49  5062.3  990.05
  5067.4  990.02  5114.4  992.41  5119.5  992.45  5146.7  993.70  5197.6  995.31
#Mann=3,-1,0
  4691.8    0.05       0  4983.7    0.03       0  4987.7    0.05       0
Bank Sta=4983.7,4987.7
Exp/Cntr=0.3,0.1

Type RM Length L Ch R = 1,4849,474,474,474
BEGIN DESCRIPTION:
LITTLE LLANO 006 7.0
END DESCRIPTION:
XS GIS Cut Line= 3
      2869655.67     10241553.10      2869496.50     10241475.00
      2869105.67     10241653.12
#Sta/Elev= 30
  4822.7  993.73  4867.2  991.50  4921.1  987.65  4926.7  987.58  4943.6  985.69
  4949.2  985.68  4956.4  984.83  4966.1  984.64  4994.1  982.95  4995.7  981.93
  4995.9  981.43  4999.4  981.43  4999.7  981.93  5003.2  981.93  5006.9  982.82
  5030.0  984.74  5044.9  985.02  5099.1  984.67  5150.7  985.96  5179.3  986.16
  5202.3  987.12  5225.4  987.27  5231.7  988.14  5242.7  987.75  5248.4  988.47
  5271.4  989.22  5323.0  990.14  5363.6  991.51  5374.6  992.28  5429.5  993.72
#Mann=3,-1,0
  4822.7    0.05       0  4995.7    0.03       0  4999.7    0.05       0
Bank Sta=4995.7,4999.7
Exp/Cntr=0.3,0.1

Type RM Length L Ch R = 1,4375,489,489,489
BEGIN DESCRIPTION:
LITTLE LLANO 006 6.0
END DESCRIPTION:
XS GIS Cut Line= 3
      2869855.66     10241403.10      2869387.25     10241066.00
      2868805.68     10240703.11
#Sta/Elev= 30
  4422.9  996.15  4486.7  994.77  4587.4  989.67  4681.6  986.69  4759.2  985.11
  4839.0  984.17  4859.8  984.47  4931.0  982.15  4975.2  982.30  4998.2  980.17
  5015.2  980.07  5015.5  979.57  5019.0  979.57  5019.2  980.07  5032.6  983.80
  5090.4  987.45  5132.8  988.15  5263.8  987.35  5331.0  983.63  5373.5  983.23
  5394.7  980.57  5425.4  982.11  5431.3  981.79  5438.0  983.78  5446.6  985.01
  5452.5  984.89  5467.8  986.33  5525.7  987.60  5635.4  993.58  5685.5  995.32
#Mann=3,-1,0
  4422.9    0.05       0  5015.2    0.05       0  5019.2    0.05       0
Bank Sta=5015.2,5019.2
Exp/Cntr=0.3,0.1

Type RM Length L Ch R = 1,3886,469,469,469
BEGIN DESCRIPTION:
LITTLE LLANO 006 5.0
END DESCRIPTION:
XS GIS Cut Line= 3
      2869955.70     10240953.13      2869659.25     10240663.00
      2868755.70     10240653.11
#Sta/Elev= 30
  4585.2  989.98  4648.9  986.59  4670.0  986.58  4790.3  981.39  4811.5  981.84
  4832.8  981.13  4861.0  977.99  4873.2  977.65  4873.4  977.15  4877.2  977.65
  4896.3  979.31  4945.9  979.90  4981.2  978.43  5023.6  978.17  5043.6  981.11
  5063.6  982.44  5123.6  984.39  5203.6  985.27  5273.6  984.84  5353.6  981.86
  5442.7  980.34  5453.6  979.55  5483.6  980.18  5503.6  978.55  5533.6  978.90
  5583.6  983.20  5663.6  986.42  5743.6  991.82  5803.6  994.63  5903.6  997.71
#Mann=3,-1,0
  4585.2    0.05       0  4873.2    0.03       0  4877.2    0.05       0
Bank Sta=4873.2,4877.2
Exp/Cntr=0.3,0.1

Type RM Length L Ch R = 1,3417,482,482,482
BEGIN DESCRIPTION:
LITTLE LLANO 006 4.0
END DESCRIPTION:
XS GIS Cut Line= 3
      2869955.67     10240553.10      2869810.00     10240433.00
      2868905.64     10240553.12
#Sta/Elev= 30
  4811.2  985.87  4853.5  984.03  4867.9  982.19  4896.5  980.23  4939.6  978.03
  4946.0  978.29  4974.7  975.77  4981.2  976.02  4993.5  973.63  4993.8  973.13
  4997.3  973.13  4997.5  973.63  4999.6  974.27  5014.4  974.77  5024.5  976.90
  5034.2  977.88  5125.4  980.35  5269.2  982.29  5448.2  981.12  5468.4  979.74
  5488.6  976.15  5499.1  976.86  5508.7  978.52  5518.8  978.96  5572.4  980.50
  5710.5  986.77  5724.0  986.70  5797.3  989.99  5802.3  989.68  5912.3  993.59
#Mann=3,-1,0
  4811.2    0.05       0  4993.5    0.05       0  4997.5    0.05       0
Bank Sta=4993.5,4997.5
Exp/Cntr=0.3,0.1

Type RM Length L Ch R = 1,2935,962,962,962
BEGIN DESCRIPTION:
LITTLE LLANO 006 3.0
END DESCRIPTION:
XS GIS Cut Line= 3
      2870155.70     10240253.14      2870056.00     10240128.00
      2869155.71     10240053.11
#Sta/Elev= 30
  4840.0  982.77  4904.0  981.01  4946.5  980.46  4960.9  978.67  4967.9  976.42
  4975.4  974.97  4981.8  972.42  4989.8  972.21  5002.7  972.43  5030.4  975.40
  5122.5  976.22  5201.0  976.03  5251.2  975.11  5301.4  975.79  5351.5  972.15
  5358.6  972.72  5363.6  972.06  5371.6  972.30  5399.7  971.57  5399.9  971.07
  5403.4  971.07  5403.7  971.57  5411.7  972.54  5421.8  972.80  5451.9  972.38
  5484.1  975.40  5582.3  977.60  5712.8  982.12  5845.7  985.16  5903.4  987.23
#Mann=3,-1,0
  4840.0    0.05       0  5399.7    0.05       0  5403.7    0.05       0
Bank Sta=5399.7,5403.7
Exp/Cntr=0.3,0.1

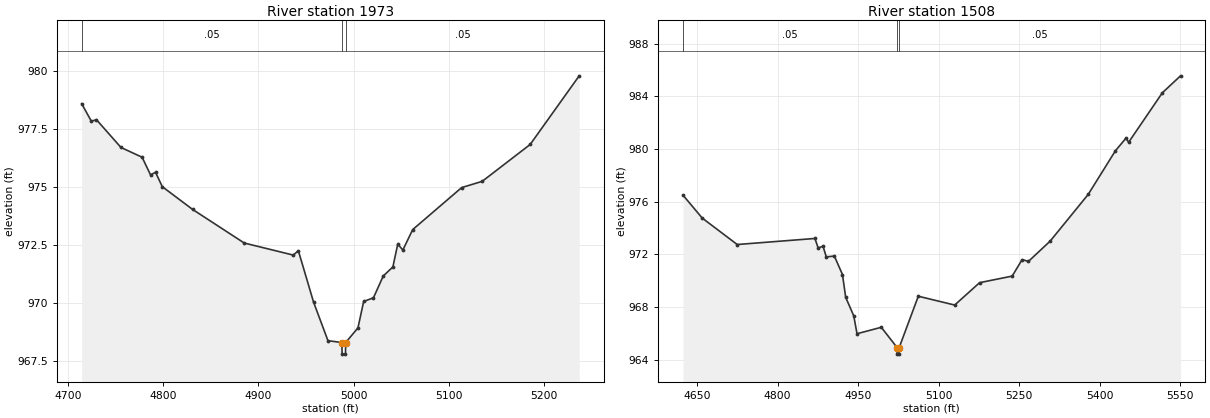
Type RM Length L Ch R = 1,1973,465,465,465
BEGIN DESCRIPTION:
LITTLE LLANO 006 2.0
END DESCRIPTION:
XS GIS Cut Line= 3
      2869855.65     10239603.10      2869586.00     10239509.00
      2869355.68     10239453.11
#Sta/Elev= 30
  4714.4  978.61  4724.6  977.85  4729.9  977.92  4755.7  976.72  4777.9  976.30
  4786.7  975.54  4792.0  975.65  4799.1  975.03  4830.9  974.05  4885.2  972.60
  4936.7  972.08  4942.0  972.27  4958.0  970.05  4973.1  968.39  4987.7  968.31
  4988.0  967.81  4991.5  967.81  4991.7  968.31  5004.6  968.94  5010.6  970.08
  5020.9  970.24  5031.2  971.18  5041.3  971.57  5046.4  972.55  5051.8  972.30
  5062.1  973.18  5113.5  974.99  5135.1  975.26  5185.5  976.85  5237.0  979.81
#Mann=3,-1,0
  4714.4    0.05       0  4987.7    0.03       0  4991.7    0.05       0
Bank Sta=4987.7,4991.7
Exp/Cntr=0.3,0.1

Type RM Length L Ch R = 1,1508,0,0,0
BEGIN DESCRIPTION:
LITTLE LLANO 006 1.0
END DESCRIPTION:
XS GIS Cut Line= 3
      2869955.66     10239403.08      2869749.75     10239088.00
      2869205.73     10239003.12
#Sta/Elev= 30
  4623.6  976.50  4659.4  974.76  4724.6  972.75  4869.4  973.21  4875.4  972.49
  4884.5  972.62  4890.5  971.81  4905.6  971.87  4920.7  970.47  4926.7  968.74
  4941.8  967.32  4947.8  965.97  4993.1  966.46  5022.4  964.92  5022.6  964.42
  5026.1  964.42  5026.4  964.92  5062.0  968.82  5129.8  968.15  5176.2  969.85
  5236.9  970.35  5255.4  971.60  5267.3  971.47  5307.7  973.01  5378.6  976.56
  5429.2  979.87  5448.9  980.83  5453.9  980.52  5516.7  984.28  5550.6  985.57
#Mann=3,-1,0
  4623.6    0.05       0  5022.4    0.03       0  5026.4    0.05       0
Bank Sta=5022.4,5026.4
Exp/Cntr=0.3,0.1

Chan Stop Cuts=-1