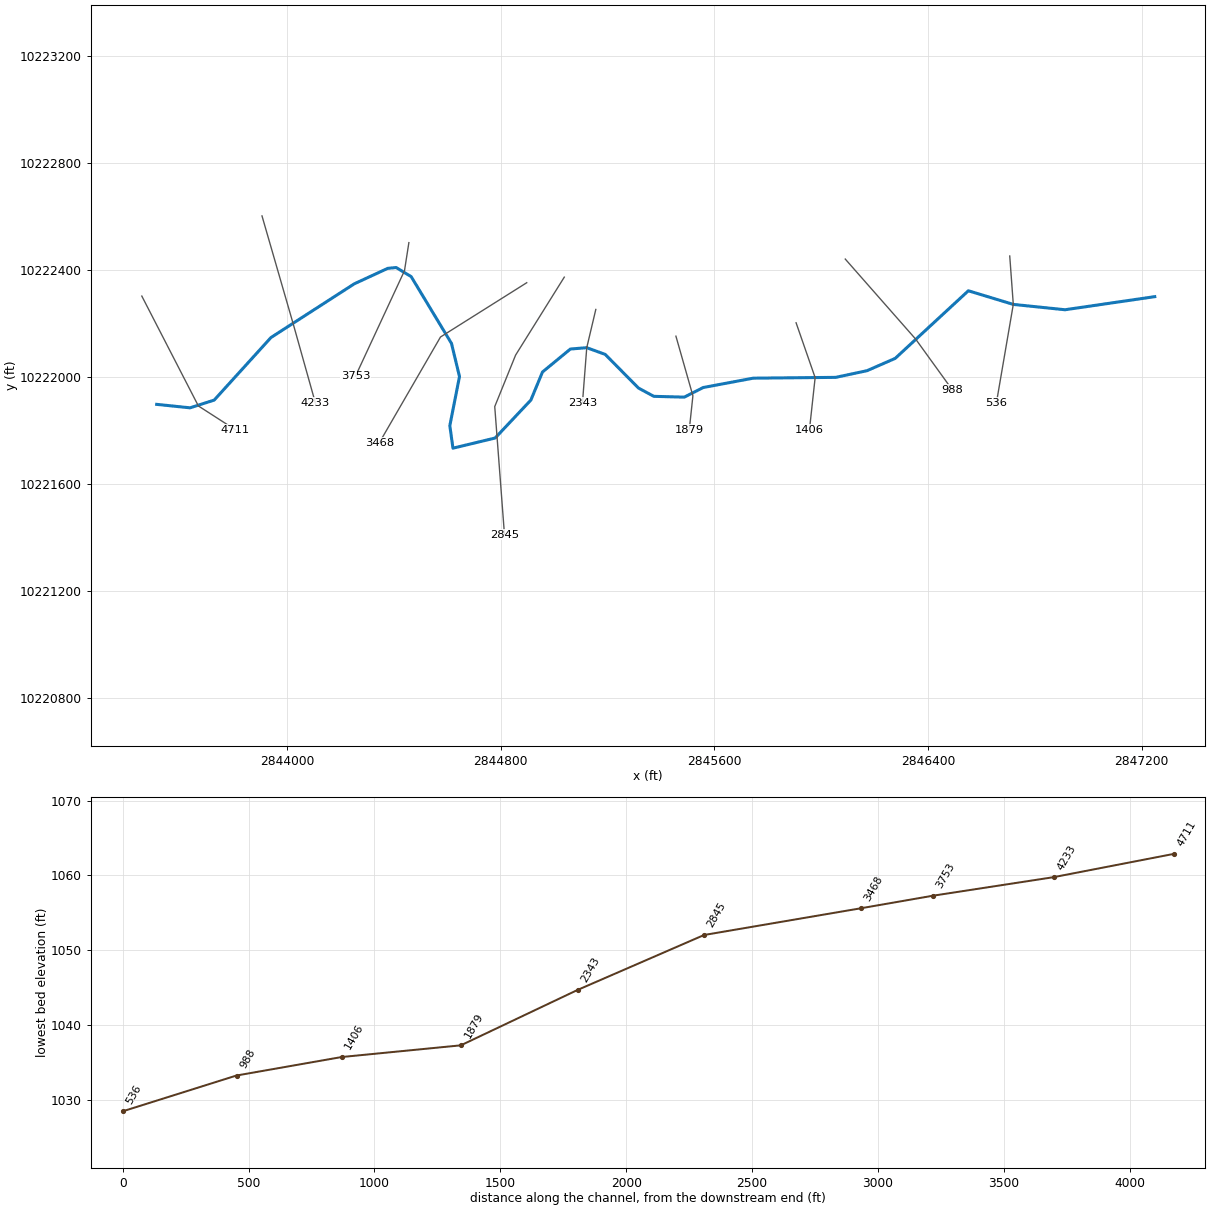
--- LITTLE LLANO 010.prj (project) ---

Proj Title=LITTLE LLANO 010 Base Level Engineering
Current Plan=p01
Default Exp/Contr=0.3,0.1
English Units
Geom File=g01
Flow File=f01
Plan File=p01
BEGIN DESCRIPTION:
LITTLE LLANO 010
END DESCRIPTION:

--- LITTLE LLANO 010.p01 (plan) ---

Plan Title=Multiple Run
Short Identifier=Multiple
Geom File=g01
Flow File=f01
Subcritical Flow
K Sum by GR= 0
Std Step Tol= 0.01
Critical Tol= 0.01
Num of Std Step Trials= 20
Max Error Tol= 0.3
Flow Tol Ratio= 0.001
Split Flow NTrial= 30
Split Flow Tol= 0.02
Split Flow Ratio= 0.02
Log Output Level= 0
Friction Slope Method= 1
Unsteady Friction Slope Method= 2
Unsteady Bridges Friction Slope Method= 1
Parabolic Critical Depth
Global Vel Dist=  1 , 1 , 1
Global Log Level= 0
CheckData=True
Encroach Param= -1, 0, 0, 0
BEGIN DESCRIPTION:
Multiple Run
END DESCRIPTION:

--- LITTLE LLANO 010.f01 (steady flow) ---

Flow Title=Multiple
Number of Profiles=7
Profile Names=10-year,25-year,50-year,1pct_min,100-year,1pct_plu,500-year
River Rch & RM= LITTLE LLANO 010,Reach-1,4711
     128     264     428     229     691    2085    1920
Boundary for River Rch & Prof#=LITTLE LLANO 010,Reach-1,1
Up Type=0
Dn Type=3
Dn Slope=0.005
Boundary for River Rch & Prof#=LITTLE LLANO 010,Reach-1,2
Up Type=0
Dn Type=3
Dn Slope=0.005
Boundary for River Rch & Prof#=LITTLE LLANO 010,Reach-1,3
Up Type=0
Dn Type=3
Dn Slope=0.005
Boundary for River Rch & Prof#=LITTLE LLANO 010,Reach-1,4
Up Type=0
Dn Type=3
Dn Slope=0.005
Boundary for River Rch & Prof#=LITTLE LLANO 010,Reach-1,5
Up Type=0
Dn Type=3
Dn Slope=0.005
Boundary for River Rch & Prof#=LITTLE LLANO 010,Reach-1,6
Up Type=0
Dn Type=3
Dn Slope=0.005
Boundary for River Rch & Prof#=LITTLE LLANO 010,Reach-1,7
Up Type=0
Dn Type=3
Dn Slope=0.005

--- LITTLE LLANO 010.g01 (geometry) ---

Geom Title=Existing Conditions

River Reach=LITTLE LLANO 010,Reach-1
Reach XY= 30
      2843511.25     10221898.00      2843636.25     10221885.00
      2843726.75     10221914.00      2843939.25     10222148.00
      2844251.25     10222349.00      2844376.75     10222407.00
      2844408.00     10222410.00      2844464.25     10222376.00
      2844615.25     10222126.00      2844645.25     10222002.00
      2844609.00     10221818.00      2844620.75     10221734.00
      2844778.75     10221772.00      2844912.50     10221914.00
      2844956.00     10222019.00      2845060.50     10222105.00
      2845121.75     10222110.00      2845190.75     10222085.00
      2845315.50     10221959.00      2845372.75     10221928.00
      2845487.00     10221925.00      2845558.00     10221961.00
      2845745.25     10221996.00      2846054.00     10221999.00
      2846171.50     10222024.00      2846276.75     10222070.00
      2846550.75     10222323.00      2846719.00     10222272.00
      2846912.75     10222252.00      2847248.75     10222301.00

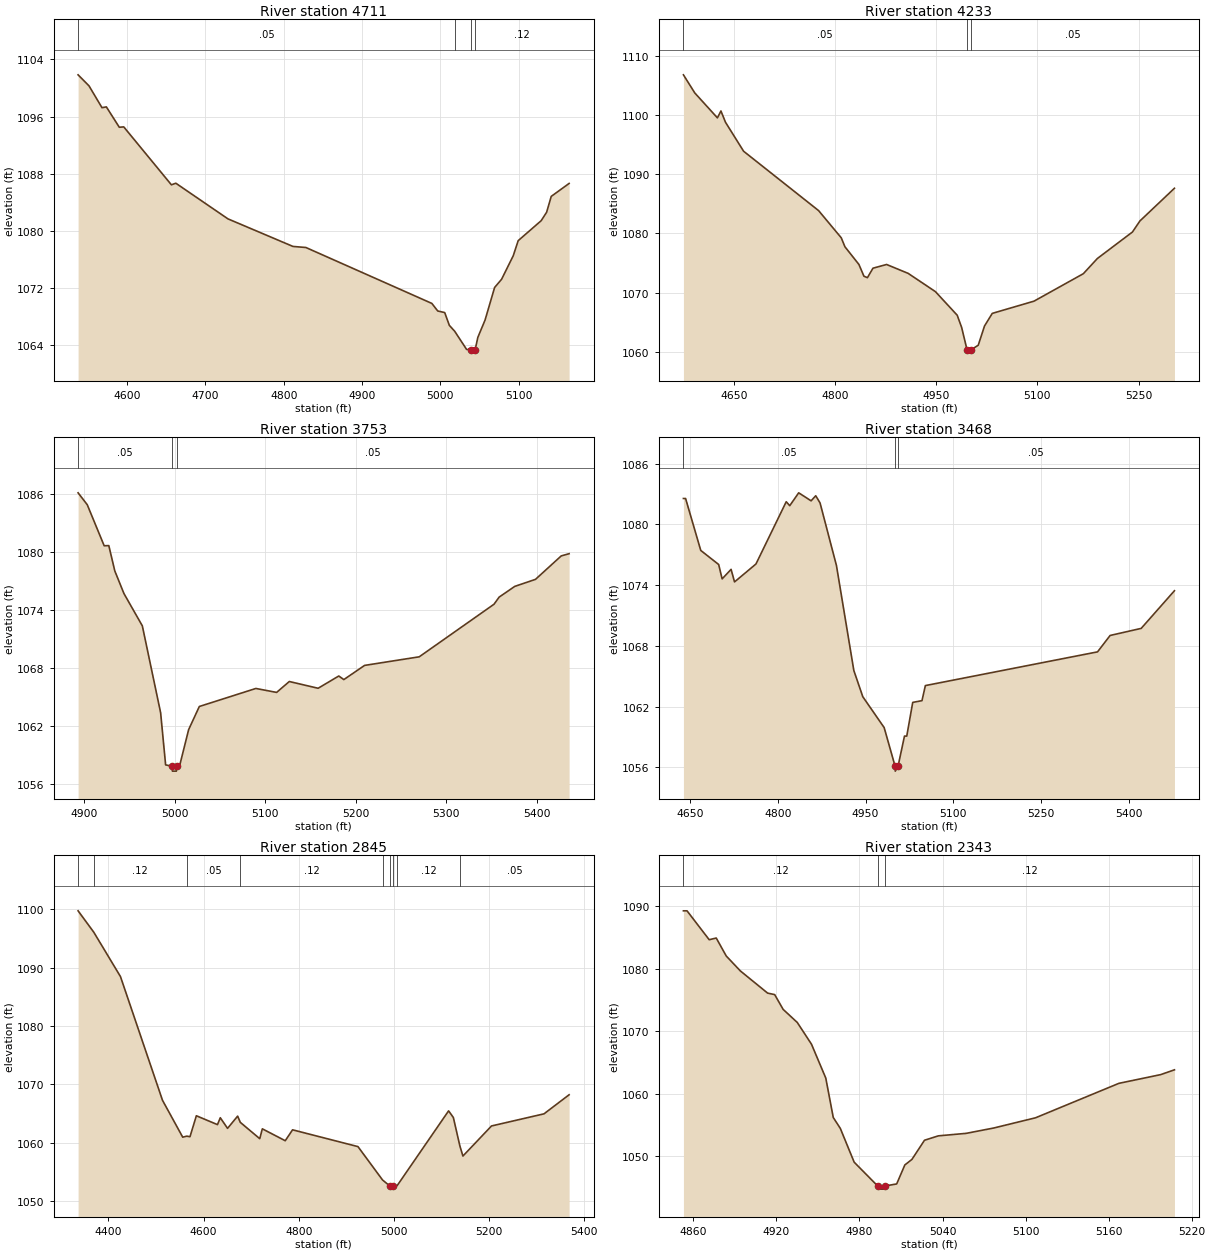
Type RM Length L Ch R = 1,4711,478,478,478
BEGIN DESCRIPTION:
LITTLE LLANO 010 10.0
END DESCRIPTION:
XS GIS Cut Line= 3
      2843455.67     10222303.14      2843667.50     10221892.00
      2843805.68     10221803.11
#Sta/Elev= 30
  4537.5 1101.85  4551.4 1100.31  4568.0 1097.25  4573.6 1097.36  4590.1 1094.51
  4595.8 1094.56  4656.6 1086.45  4662.3 1086.67  4728.8 1081.68  4811.8 1077.82
  4828.3 1077.67  4989.1 1069.84  4996.6 1068.78  5005.5 1068.56  5011.4 1066.77
  5018.2 1065.95  5033.5 1063.39  5039.3 1063.38  5039.7 1062.88  5044.4 1063.38
  5047.8 1065.09  5057.0 1067.51  5069.2 1072.07  5078.1 1073.22  5093.0 1076.52
  5099.3 1078.63  5128.6 1081.42  5135.6 1082.61  5141.5 1084.83  5164.3 1086.64
#Mann=4,-1,0
  4537.5    0.05       0  5018.2    0.12       0  5039.3    0.05       0
  5044.4    0.12       0
Bank Sta=5039.3,5044.4
Exp/Cntr=0.3,0.1

Type RM Length L Ch R = 1,4233,480,480,480
BEGIN DESCRIPTION:
LITTLE LLANO 010 9.0
END DESCRIPTION:
XS GIS Cut Line= 3
      2843905.70     10222603.07      2844023.75     10222195.00
      2844105.69     10221903.08
#Sta/Elev= 30
  4575.2 1106.83  4592.0 1103.77  4625.6 1099.55  4630.8 1100.72  4637.6 1098.80
  4664.4 1093.91  4775.6 1083.87  4809.2 1079.27  4814.6 1077.76  4835.4 1074.76
  4842.8 1072.78  4848.0 1072.53  4856.2 1074.13  4876.4 1074.76  4908.3 1073.26
  4948.8 1070.17  4981.1 1066.18  4987.7 1064.11  4995.8 1060.27  4996.2 1059.77
  5000.9 1060.27  5012.3 1061.11  5021.6 1064.36  5033.1 1066.49  5095.0 1068.56
  5168.1 1073.20  5188.9 1075.77  5240.9 1080.25  5252.0 1082.12  5303.2 1087.65
#Mann=3,-1,0
  4575.2    0.05       0  4995.8    0.03       0  5000.9    0.05       0
Bank Sta=4995.8,5000.9
Exp/Cntr=0.3,0.1

Type RM Length L Ch R = 1,3753,285,285,285
BEGIN DESCRIPTION:
LITTLE LLANO 010 8.0
END DESCRIPTION:
XS GIS Cut Line= 3
      2844455.69     10222503.12      2844439.25     10222398.00
      2844255.67     10222003.08
#Sta/Elev= 30
  4893.6 1086.14  4903.7 1084.91  4922.4 1080.65  4927.5 1080.67  4934.1 1078.05
  4944.2 1075.70  4964.5 1072.35  4984.7 1063.34  4990.2 1057.94  4997.3 1057.79
  4997.7 1057.29  5002.1 1057.29  5002.5 1057.79  5005.5 1057.79  5015.6 1061.59
  5027.4 1063.99  5089.8 1065.86  5112.7 1065.45  5126.7 1066.58  5158.5 1065.88
  5181.3 1067.15  5186.9 1066.78  5209.8 1068.25  5270.1 1069.14  5352.6 1074.59
  5358.3 1075.33  5375.5 1076.44  5398.4 1077.17  5426.8 1079.60  5435.5 1079.83
#Mann=3,-1,0
  4893.6    0.05       0  4997.3    0.05       0  5002.5    0.05       0
Bank Sta=4997.3,5002.5
Exp/Cntr=0.3,0.1

Type RM Length L Ch R = 1,3468,623,623,623
BEGIN DESCRIPTION:
Mapping XS d9307902
END DESCRIPTION:
XS GIS Cut Line= 3
      2844896.99     10222353.13      2844574.10     10222150.02
      2844344.95     10221754.23
#Sta/Elev= 30
  4638.9 1082.55  4642.6 1082.55  4668.5 1077.42  4699.1 1076.03  4705.0 1074.61
  4720.3 1075.55  4726.2 1074.31  4762.8 1076.08  4814.5 1082.23  4820.5 1081.84
  4835.8 1083.11  4857.0 1082.32  4864.9 1082.82  4872.3 1082.11  4900.3 1075.93
  4930.0 1065.56  4945.3 1062.97  4981.8 1059.92  5000.4 1056.12  5000.8 1055.62
  5005.6 1056.12  5016.5 1059.08  5020.4 1059.08  5030.6 1062.41  5046.4 1062.58
  5052.2 1064.07  5346.3 1067.40  5367.8 1069.02  5420.9 1069.72  5477.7 1073.44
#Mann=3,-1,0
  4638.9    0.05       0  5000.4    0.05       0  5005.6    0.05       0
Bank Sta=5000.4,5005.6
Exp/Cntr=0.3,0.1

Type RM Length L Ch R = 1,2845,502,502,502
BEGIN DESCRIPTION:
Mapping XS 4b97e67e
END DESCRIPTION:
XS GIS Cut Line= 4
      2845037.66     10222374.02      2844855.35     10222082.31
      2844777.22     10221889.61      2844813.68     10221410.43
#Sta/Elev= 30
  4336.1 1099.77  4369.2 1096.09  4425.2 1088.50  4513.6 1067.28  4556.1 1060.96
  4564.7 1061.13  4571.4 1061.04  4584.8 1064.63  4629.2 1063.11  4635.1 1064.29
  4650.4 1062.47  4671.6 1064.57  4677.2 1063.50  4718.1 1060.70  4723.5 1062.39
  4771.7 1060.35  4787.1 1062.22  4924.6 1059.34  4976.3 1053.62  4992.2 1052.55
  4992.6 1052.05  4997.4 1052.55  5007.1 1052.66  5115.2 1065.47  5125.2 1064.33
  5138.9 1059.46  5145.3 1057.72  5205.4 1062.88  5315.8 1064.96  5368.6 1068.23
#Mann=9,-1,0
  4336.1    0.05       0  4369.2    0.12       0  4564.7    0.05       0
  4677.2    0.12       0  4976.3    0.05       0  4992.2    0.05       0
  4997.4    0.05       0  5007.1    0.12       0  5138.9    0.05       0
Bank Sta=4992.2,4997.4
Exp/Cntr=0.3,0.1

Type RM Length L Ch R = 1,2343,464,464,464
BEGIN DESCRIPTION:
LITTLE LLANO 010 5.0
END DESCRIPTION:
XS GIS Cut Line= 3
      2845155.69     10222253.13      2845121.75     10222110.00
      2845105.69     10221903.12
#Sta/Elev= 30
  4852.9 1089.23  4855.5 1089.23  4871.5 1084.61  4876.6 1084.88  4883.8 1082.01
  4894.0 1079.62  4913.7 1076.07  4918.8 1075.83  4924.9 1073.47  4935.1 1071.38
  4945.4 1067.89  4955.7 1062.48  4961.1 1056.18  4966.2 1054.43  4976.2 1049.03
  4993.2 1045.22  4993.6 1044.72  4998.0 1044.72  4998.4 1045.22  5006.9 1045.55
  5012.8 1048.59  5017.9 1049.47  5027.0 1052.54  5037.0 1053.24  5057.1 1053.64
  5077.1 1054.50  5107.2 1056.13  5167.4 1061.64  5197.5 1063.03  5207.5 1063.80
#Mann=3,-1,0
  4852.9    0.12       0  4993.2    0.07       0  4998.4    0.12       0
Bank Sta=4993.2,4998.4
Exp/Cntr=0.3,0.1

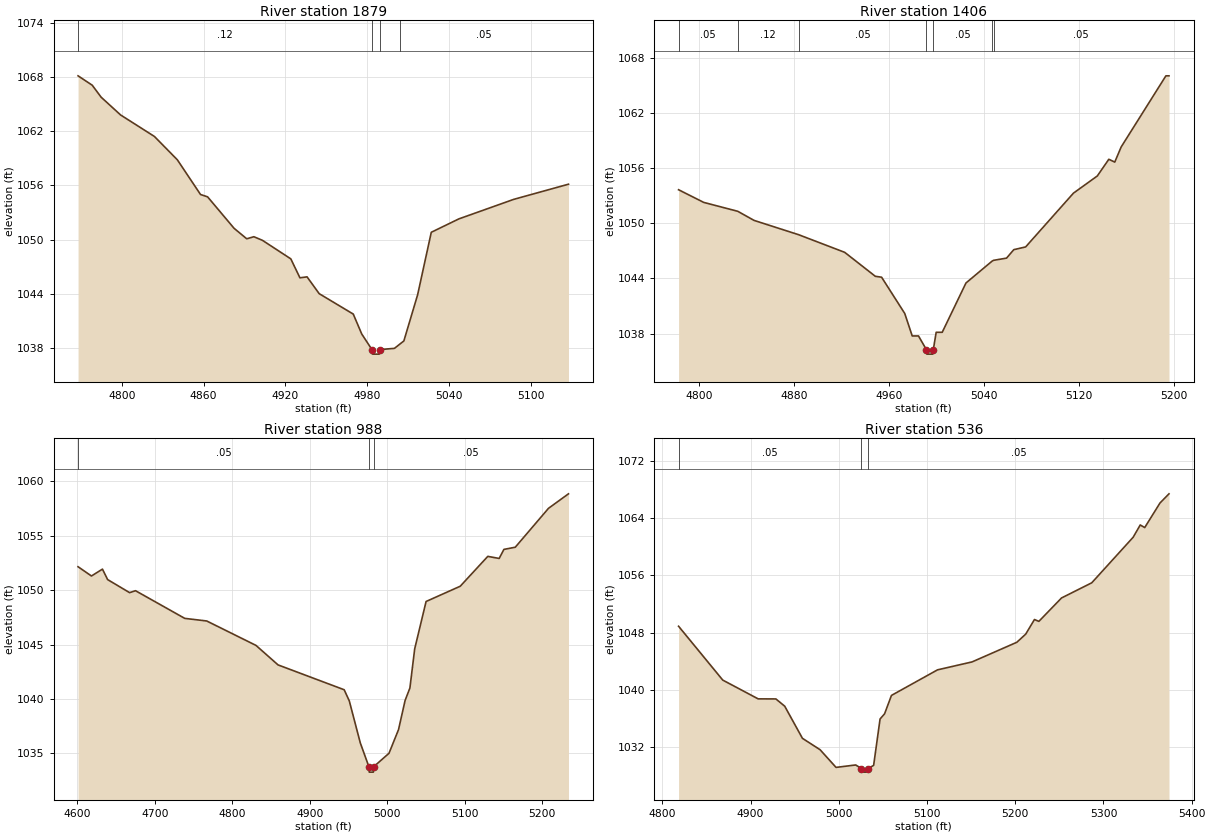
Type RM Length L Ch R = 1,1879,473,473,473
BEGIN DESCRIPTION:
LITTLE LLANO 010 4.0
END DESCRIPTION:
XS GIS Cut Line= 3
      2845455.68     10222153.12      2845519.25     10221930.00
      2845505.69     10221803.12
#Sta/Elev= 30
  4768.0 1068.11  4778.4 1067.07  4784.9 1065.75  4799.2 1063.78  4824.0 1061.40
  4840.8 1058.82  4857.8 1054.98  4863.0 1054.72  4882.4 1051.24  4891.7 1050.08
  4896.9 1050.31  4903.2 1049.91  4924.0 1047.86  4930.7 1045.76  4935.9 1045.87
  4944.8 1044.01  4969.8 1041.75  4976.0 1039.55  4983.5 1037.82  4983.9 1037.32
  4988.8 1037.32  4989.3 1037.82  5000.0 1037.96  5003.7 1038.40  5006.9 1038.78
  5017.0 1043.89  5027.0 1050.80  5047.2 1052.28  5087.4 1054.44  5127.6 1056.12
#Mann=4,-1,0
  4768.0    0.12       0  4983.5    0.07       0  4989.3    0.12       0
  5003.7    0.05       0
Bank Sta=4983.5,4989.3
Exp/Cntr=0.3,0.1

Type RM Length L Ch R = 1,1406,418,418,418
BEGIN DESCRIPTION:
LITTLE LLANO 010 3.0
END DESCRIPTION:
XS GIS Cut Line= 3
      2845905.67     10222203.15      2845977.00     10221998.00
      2845955.68     10221803.06
#Sta/Elev= 30
  4782.8 1053.67  4804.0 1052.29  4832.7 1051.32  4846.4 1050.33  4884.0 1048.77
  4922.8 1046.85  4948.6 1044.24  4953.9 1044.14  4973.4 1040.19  4979.7 1037.74
  4985.0 1037.74  4991.6 1036.26  4992.1 1035.76  4997.0 1035.76  4997.5 1036.26
  4999.9 1038.14  5005.0 1038.14  5025.0 1043.51  5047.1 1045.90  5048.3 1045.98
  5059.2 1046.22  5065.3 1047.14  5075.3 1047.44  5115.6 1053.30  5135.7 1055.17
  5145.4 1056.99  5150.4 1056.68  5155.8 1058.33  5193.5 1066.08  5196.1 1066.08
#Mann=7,-1,0
  4782.8    0.05       0  4832.7    0.12       0  4884.0    0.05       0
  4991.6    0.05       0  4997.5    0.05       0  5047.1    0.12       0
  5048.3    0.05       0
Bank Sta=4991.6,4997.5
Exp/Cntr=0.3,0.1

Type RM Length L Ch R = 1,988,452,452,452
BEGIN DESCRIPTION:
LITTLE LLANO 010 2.0
END DESCRIPTION:
XS GIS Cut Line= 3
      2846089.75     10222441.66      2846353.50     10222142.00
      2846490.70     10221952.19
#Sta/Elev= 30
  4600.8 1052.14  4618.1 1051.29  4632.3 1051.92  4639.0 1050.96  4667.4 1049.76
  4675.0 1049.94  4738.6 1047.40  4767.0 1047.16  4830.6 1044.92  4859.1 1043.13
  4944.5 1040.85  4951.1 1039.83  4965.3 1035.98  4976.4 1033.79  4976.9 1033.29
  4982.2 1033.29  4982.7 1033.79  5002.4 1035.02  5014.7 1037.19  5023.2 1039.87
  5029.4 1041.01  5035.6 1044.61  5050.3 1048.95  5094.4 1050.35  5130.0 1053.09
  5144.7 1052.90  5150.8 1053.73  5165.5 1053.93  5208.4 1057.50  5234.2 1058.83
#Mann=3,-1,0
  4600.8    0.05       0  4976.4    0.03       0  4982.7    0.05       0
Bank Sta=4976.4,4982.7
Exp/Cntr=0.3,0.1

Type RM Length L Ch R = 1,536,0,0,0
BEGIN DESCRIPTION:
LITTLE LLANO 010 1.0
END DESCRIPTION:
XS GIS Cut Line= 3
      2846705.68     10222453.11      2846719.00     10222272.00
      2846655.68     10221903.09
#Sta/Elev= 30
  4818.4 1048.88  4868.5 1041.36  4908.6 1038.74  4928.7 1038.73  4938.7 1037.72
  4958.8 1033.23  4978.8 1031.64  4996.9 1029.17  5019.2 1029.51  5025.7 1029.01
  5026.2 1028.51  5032.4 1028.51  5032.9 1029.01  5039.5 1029.45  5046.8 1035.93
  5051.9 1036.65  5059.7 1039.22  5111.9 1042.79  5151.1 1043.90  5201.8 1046.64
  5211.9 1047.78  5221.8 1049.82  5226.8 1049.56  5252.5 1052.83  5286.8 1054.95
  5333.7 1061.31  5341.7 1063.02  5346.8 1062.66  5364.1 1066.09  5374.3 1067.37
#Mann=3,-1,0
  4818.4    0.05       0  5025.7    0.05       0  5032.9    0.05       0
Bank Sta=5025.7,5032.9
Exp/Cntr=0.3,0.1

Chan Stop Cuts=-1