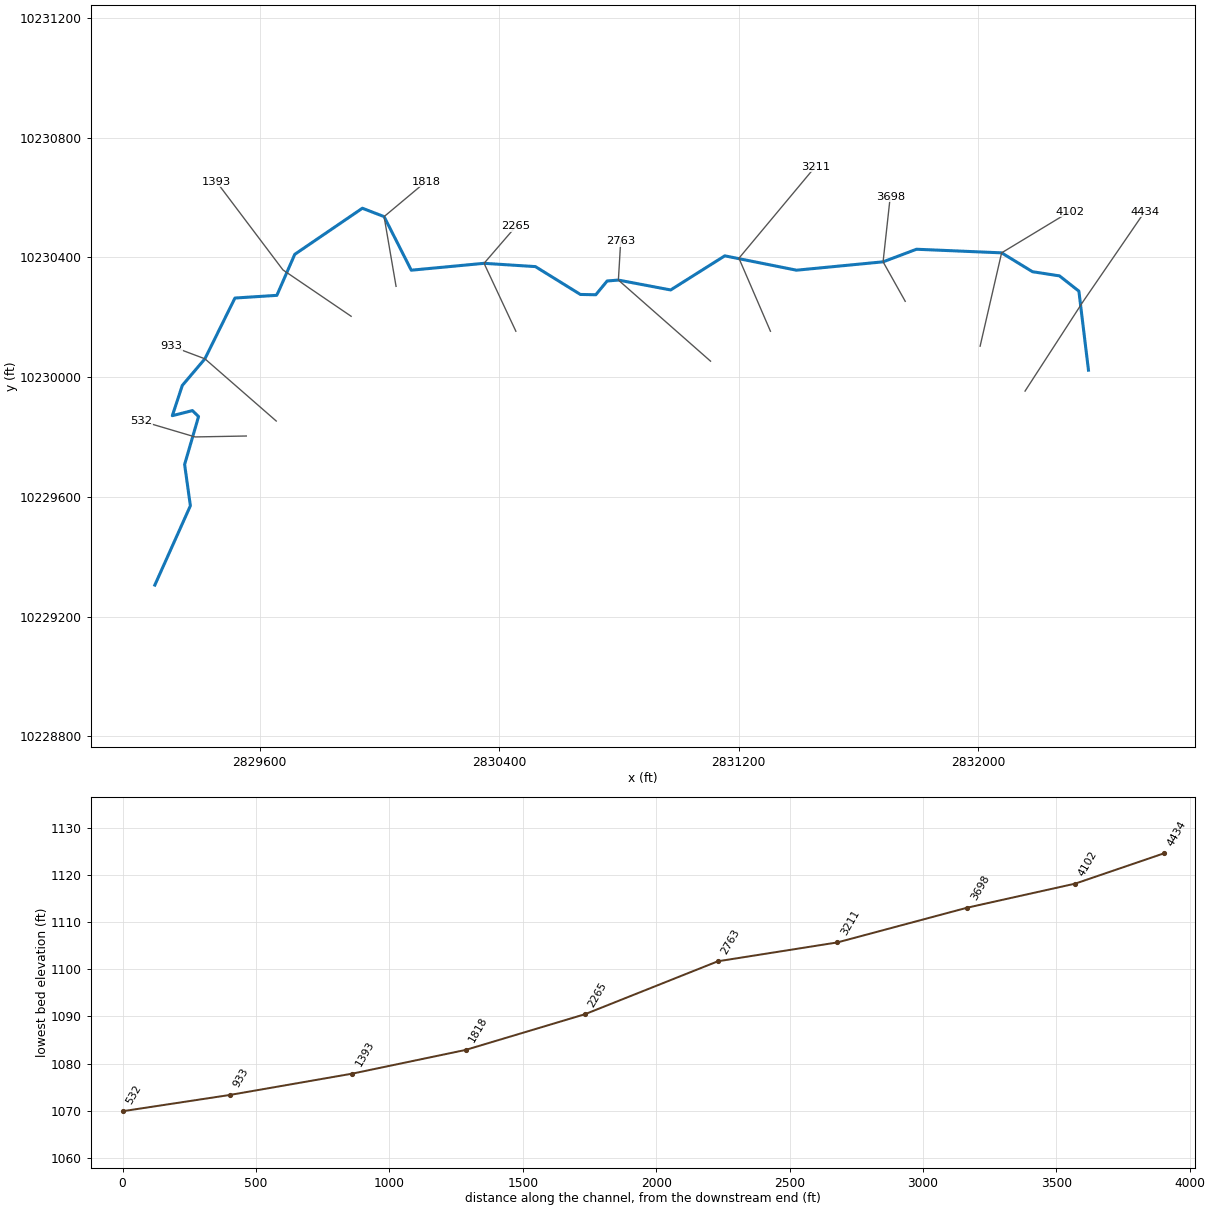
--- LITTLE LLANO 014.prj (project) ---

Proj Title=LITTLE LLANO 014 Base Level Engineering
Current Plan=p01
Default Exp/Contr=0.3,0.1
English Units
Geom File=g01
Flow File=f01
Plan File=p01
BEGIN DESCRIPTION:
LITTLE LLANO 014
END DESCRIPTION:

--- LITTLE LLANO 014.p01 (plan) ---

Plan Title=Multiple Run
Short Identifier=Multiple
Geom File=g01
Flow File=f01
Subcritical Flow
K Sum by GR= 0
Std Step Tol= 0.01
Critical Tol= 0.01
Num of Std Step Trials= 20
Max Error Tol= 0.3
Flow Tol Ratio= 0.001
Split Flow NTrial= 30
Split Flow Tol= 0.02
Split Flow Ratio= 0.02
Log Output Level= 0
Friction Slope Method= 1
Unsteady Friction Slope Method= 2
Unsteady Bridges Friction Slope Method= 1
Parabolic Critical Depth
Global Vel Dist=  1 , 1 , 1
Global Log Level= 0
CheckData=True
Encroach Param= -1, 0, 0, 0
BEGIN DESCRIPTION:
Multiple Run
END DESCRIPTION:

--- LITTLE LLANO 014.f01 (steady flow) ---

Flow Title=Multiple
Number of Profiles=7
Profile Names=10-year,25-year,50-year,1pct_min,100-year,1pct_plu,500-year
River Rch & RM= LITTLE LLANO 014,Reach-1,4434
      30      45      64      31      93     280     216
Boundary for River Rch & Prof#=LITTLE LLANO 014,Reach-1,1
Up Type=0
Dn Type=3
Dn Slope=0.005
Boundary for River Rch & Prof#=LITTLE LLANO 014,Reach-1,2
Up Type=0
Dn Type=3
Dn Slope=0.005
Boundary for River Rch & Prof#=LITTLE LLANO 014,Reach-1,3
Up Type=0
Dn Type=3
Dn Slope=0.005
Boundary for River Rch & Prof#=LITTLE LLANO 014,Reach-1,4
Up Type=0
Dn Type=3
Dn Slope=0.005
Boundary for River Rch & Prof#=LITTLE LLANO 014,Reach-1,5
Up Type=0
Dn Type=3
Dn Slope=0.005
Boundary for River Rch & Prof#=LITTLE LLANO 014,Reach-1,6
Up Type=0
Dn Type=3
Dn Slope=0.005
Boundary for River Rch & Prof#=LITTLE LLANO 014,Reach-1,7
Up Type=0
Dn Type=3
Dn Slope=0.005

--- LITTLE LLANO 014.g01 (geometry) ---

Geom Title=Existing Conditions

River Reach=LITTLE LLANO 014,Reach-1
Reach XY= 30
      2832367.50     10230023.00      2832335.50     10230287.00
      2832270.75     10230338.00      2832180.50     10230352.00
      2832077.50     10230415.00      2831793.25     10230427.00
      2831681.75     10230385.00      2831392.75     10230357.00
      2831153.25     10230405.00      2830972.50     10230291.00
      2830798.00     10230324.00      2830760.50     10230321.00
      2830722.50     10230275.00      2830671.00     10230276.00
      2830521.00     10230369.00      2830349.50     10230380.00
      2830106.50     10230357.00      2830015.75     10230536.00
      2829943.25     10230564.00      2829717.50     10230410.00
      2829657.75     10230273.00      2829517.75     10230264.00
      2829417.50     10230061.00      2829342.00     10229972.00
      2829308.75     10229871.00      2829375.75     10229888.00
      2829396.25     10229868.00      2829349.75     10229708.00
      2829369.00     10229570.00      2829250.25     10229305.00

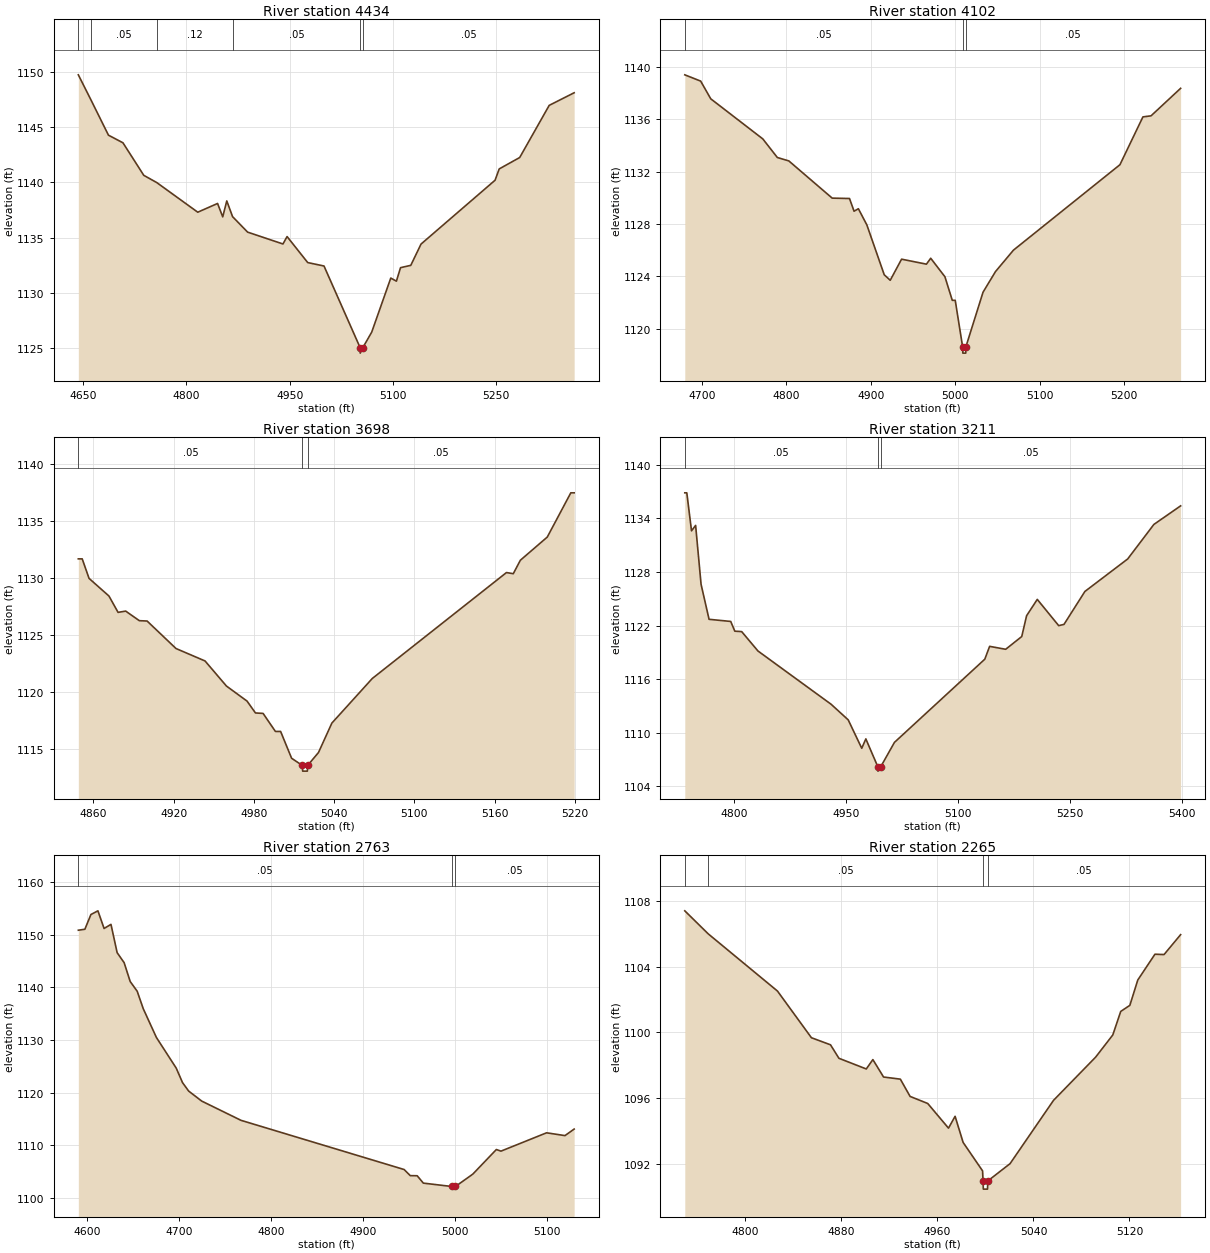
Type RM Length L Ch R = 1,4434,332,332,332
BEGIN DESCRIPTION:
LITTLE LLANO 014 10.0
END DESCRIPTION:
XS GIS Cut Line= 3
      2832155.71     10229953.14      2832350.00     10230253.00
      2832555.67     10230553.09
#Sta/Elev= 30
  4642.7 1149.70  4660.7 1147.48  4686.5 1144.25  4707.6 1143.56  4737.9 1140.62
  4756.7 1139.97  4816.4 1137.29  4845.2 1138.08  4852.7 1136.87  4858.6 1138.31
  4867.0 1136.89  4888.9 1135.49  4940.3 1134.42  4946.3 1135.09  4976.3 1132.74
  5000.0 1132.43  5052.5 1125.06  5052.7 1124.56  5056.5 1125.06  5069.4 1126.46
  5097.1 1131.34  5105.3 1131.06  5111.3 1132.28  5126.2 1132.49  5141.1 1134.41
  5248.8 1140.18  5254.8 1141.20  5284.6 1142.23  5327.5 1146.94  5363.8 1148.08
#Mann=6,-1,0
  4642.7    0.12       0  4660.7    0.05       0  4756.7    0.12       0
  4867.0    0.05       0  5052.5    0.05       0  5056.5    0.05       0
Bank Sta=5052.5,5056.5
Exp/Cntr=0.3,0.1

Type RM Length L Ch R = 1,4102,404,404,404
BEGIN DESCRIPTION:
LITTLE LLANO 014 9.0
END DESCRIPTION:
XS GIS Cut Line= 3
      2832005.70     10230103.16      2832077.50     10230415.00
      2832305.66     10230553.10
#Sta/Elev= 30
  4680.0 1139.39  4698.8 1138.91  4710.7 1137.56  4772.3 1134.50  4789.5 1133.08
  4803.1 1132.82  4854.4 1129.98  4874.9 1129.95  4880.3 1128.98  4885.4 1129.17
  4895.4 1127.94  4916.0 1124.13  4923.1 1123.71  4936.5 1125.32  4965.9 1124.94
  4971.0 1125.39  4987.8 1123.98  4996.5 1122.18  5000.0 1122.18  5008.7 1118.65
  5009.0 1118.15  5012.5 1118.15  5012.7 1118.65  5032.9 1122.80  5047.6 1124.37
  5068.9 1126.01  5194.9 1132.53  5222.1 1136.18  5231.7 1136.26  5266.7 1138.36
#Mann=3,-1,0
  4680.0    0.05       0  5008.7    0.05       0  5012.7    0.05       0
Bank Sta=5008.7,5012.7
Exp/Cntr=0.3,0.1

Type RM Length L Ch R = 1,3698,487,487,487
BEGIN DESCRIPTION:
LITTLE LLANO 014 8.0
END DESCRIPTION:
XS GIS Cut Line= 3
      2831755.69     10230253.11      2831681.75     10230385.00
      2831705.68     10230603.09
#Sta/Elev= 30
  4848.8 1131.67  4851.7 1131.67  4856.8 1129.96  4871.7 1128.41  4878.5 1126.98
  4884.2 1127.09  4894.4 1126.25  4900.2 1126.22  4921.8 1123.81  4943.5 1122.72
  4959.5 1120.52  4974.9 1119.20  4981.2 1118.16  4986.9 1118.12  4996.1 1116.54
  5000.0 1116.54  5008.2 1114.19  5016.2 1113.56  5016.5 1113.06  5020.0 1113.06
  5020.2 1113.56  5028.3 1114.69  5038.3 1117.27  5068.5 1121.18  5168.8 1130.47
  5173.9 1130.37  5179.2 1131.55  5199.3 1133.58  5216.9 1137.46  5219.4 1137.46
#Mann=3,-1,0
  4848.8    0.05       0  5016.2    0.03       0  5020.2    0.05       0
Bank Sta=5016.2,5020.2
Exp/Cntr=0.3,0.1

Type RM Length L Ch R = 1,3211,448,448,448
BEGIN DESCRIPTION:
LITTLE LLANO 014 7.0
END DESCRIPTION:
XS GIS Cut Line= 3
      2831305.68     10230153.11      2831200.50     10230397.00
      2831455.67     10230703.09
#Sta/Elev= 30
  4734.4 1136.87  4737.1 1136.87  4743.4 1132.61  4748.9 1133.22  4756.2 1126.62
  4766.9 1122.70  4795.9 1122.46  4801.4 1121.37  4810.6 1121.32  4832.4 1119.15
  4930.4 1113.18  4953.3 1111.43  4971.4 1108.25  4976.9 1109.30  4992.9 1106.19
  4993.2 1105.69  4996.9 1106.19  5015.2 1108.91  5136.2 1118.23  5142.7 1119.67
  5164.2 1119.34  5185.7 1120.77  5192.2 1123.10  5206.5 1124.93  5235.2 1121.99
  5242.3 1122.13  5270.3 1125.82  5327.6 1129.46  5362.7 1133.33  5398.5 1135.41
#Mann=3,-1,0
  4734.4    0.05       0  4992.9    0.03       0  4996.9    0.05       0
Bank Sta=4992.9,4996.9
Exp/Cntr=0.3,0.1

Type RM Length L Ch R = 1,2763,498,498,498
BEGIN DESCRIPTION:
LITTLE LLANO 014 6.0
END DESCRIPTION:
XS GIS Cut Line= 3
      2831105.65     10230053.14      2830798.00     10230324.00
      2830805.68     10230453.07
#Sta/Elev= 30
  4590.1 1150.84  4597.2 1151.02  4603.8 1153.82  4611.4 1154.52  4618.1 1151.17
  4625.6 1151.95  4632.3 1146.58  4639.9 1144.68  4646.5 1141.10  4654.1 1139.26
  4660.7 1135.94  4675.0 1130.48  4696.6 1124.65  4703.4 1121.91  4710.1 1120.30
  4724.3 1118.40  4767.0 1114.75  4944.4 1105.41  4951.1 1104.25  4958.6 1104.23
  4965.3 1102.83  4996.2 1102.19  4996.5 1101.69  5000.2 1102.19  5019.1 1104.54
  5044.7 1109.21  5049.7 1108.90  5099.3 1112.38  5119.3 1111.85  5129.3 1113.09
#Mann=3,-1,0
  4590.1    0.05       0  4996.2    0.03       0  5000.2    0.05       0
Bank Sta=4996.2,5000.2
Exp/Cntr=0.3,0.1

Type RM Length L Ch R = 1,2265,447,447,447
BEGIN DESCRIPTION:
LITTLE LLANO 014 5.0
END DESCRIPTION:
XS GIS Cut Line= 3
      2830455.68     10230153.12      2830349.50     10230380.00
      2830455.70     10230503.13
#Sta/Elev= 30
  4749.5 1107.40  4769.0 1106.00  4826.7 1102.52  4855.0 1099.68  4870.9 1099.25
  4877.9 1098.43  4900.7 1097.78  4906.2 1098.35  4915.1 1097.29  4929.1 1097.16
  4937.2 1096.11  4951.9 1095.68  4969.2 1094.18  4974.7 1094.90  4981.4 1093.31
  4997.6 1091.58  4998.0 1090.97  4998.2 1090.47  5001.7 1090.47  5002.0 1090.97
  5020.5 1092.02  5056.7 1095.87  5091.8 1098.50  5106.1 1099.85  5112.7 1101.28
  5120.3 1101.65  5126.9 1103.19  5141.2 1104.76  5148.8 1104.74  5162.6 1105.95
#Mann=4,-1,0
  4749.5    0.12       0  4769.0    0.05       0  4998.0    0.03       0
  5002.0    0.05       0
Bank Sta=4998,5002
Exp/Cntr=0.3,0.1

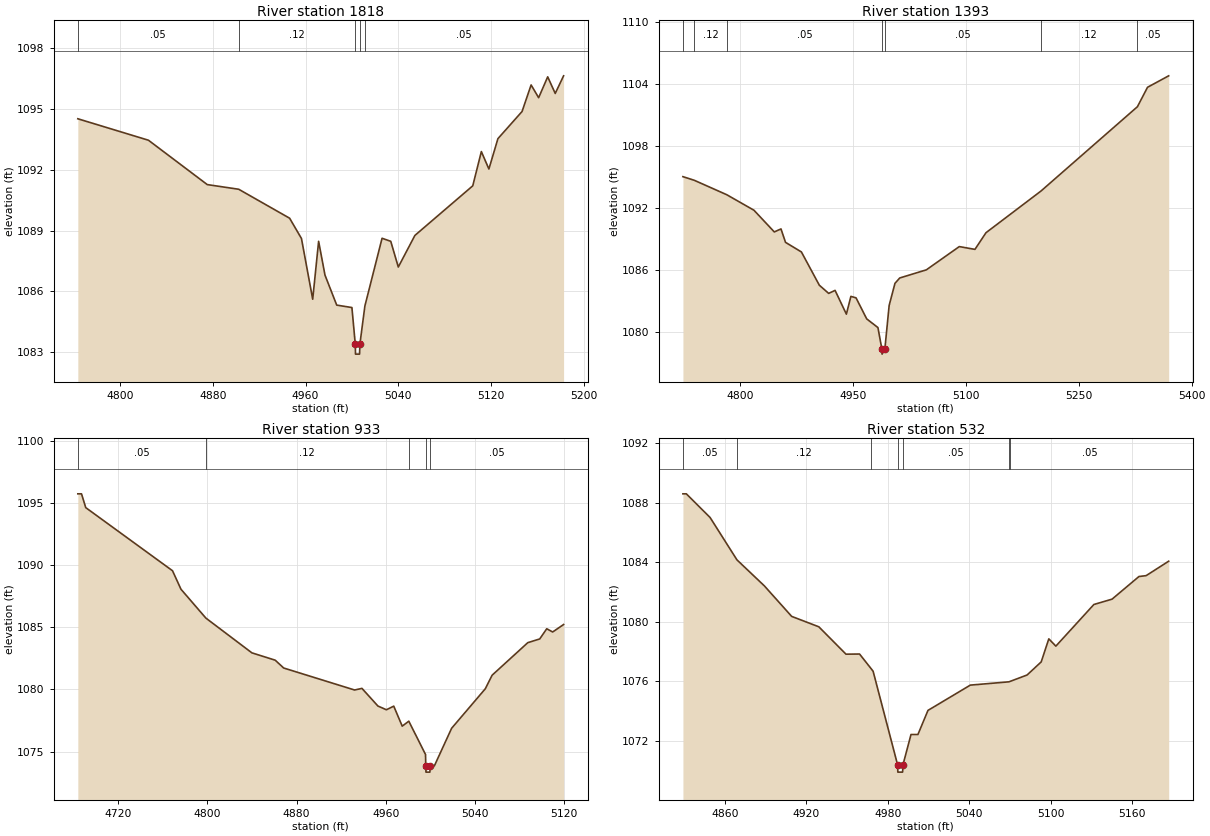
Type RM Length L Ch R = 1,1818,425,425,425
BEGIN DESCRIPTION:
LITTLE LLANO 014 4.0
END DESCRIPTION:
XS GIS Cut Line= 3
      2830055.69     10230303.10      2830015.75     10230536.00
      2830155.70     10230653.13
#Sta/Elev= 30
  4763.7 1094.52  4824.6 1093.46  4875.3 1091.27  4902.4 1091.04  4946.3 1089.61
  4956.5 1088.61  4966.2 1085.61  4971.3 1088.47  4976.8 1086.80  4986.9 1085.32
  5000.0 1085.20  5002.9 1083.40  5003.1 1082.90  5006.6 1082.90  5006.9 1083.40
  5011.2 1085.28  5026.0 1088.62  5033.5 1088.47  5040.0 1087.20  5054.3 1088.76
  5104.2 1091.21  5111.6 1092.90  5118.1 1092.04  5125.9 1093.54  5146.7 1094.88
  5154.5 1096.19  5161.0 1095.56  5168.8 1096.59  5175.3 1095.77  5182.5 1096.64
#Mann=5,-1,0
  4763.7    0.05       0  4902.4    0.12       0  5002.9    0.07       0
  5006.9    0.12       0  5011.2    0.05       0
Bank Sta=5002.9,5006.9
Exp/Cntr=0.3,0.1

Type RM Length L Ch R = 1,1393,460,460,460
BEGIN DESCRIPTION:
LITTLE LLANO 014 3.0
END DESCRIPTION:
XS GIS Cut Line= 3
      2829905.71     10230203.10      2829678.00     10230358.00
      2829455.67     10230653.13
#Sta/Elev= 30
  4724.6 1095.05  4739.6 1094.70  4782.8 1093.30  4818.9 1091.80  4845.9 1089.70
  4854.8 1089.99  4860.8 1088.69  4881.9 1087.76  4905.7 1084.54  4918.1 1083.75
  4926.6 1084.04  4941.6 1081.74  4947.6 1083.46  4954.4 1083.32  4968.6 1081.28
  4983.5 1080.44  4988.7 1078.37  4989.0 1077.87  4992.7 1078.37  4998.4 1082.59
  5006.1 1084.72  5012.4 1085.24  5047.8 1086.03  5091.5 1088.28  5112.3 1088.01
  5126.9 1089.62  5200.0 1093.66  5328.0 1101.82  5341.4 1103.70  5369.5 1104.81
#Mann=7,-1,0
  4724.6    0.05       0  4739.6    0.12       0  4782.8    0.05       0
  4988.7    0.05       0  4992.7    0.05       0  5200.0    0.12       0
  5328.0    0.05       0
Bank Sta=4988.7,4992.7
Exp/Cntr=0.3,0.1

Type RM Length L Ch R = 1,933,401,401,401
BEGIN DESCRIPTION:
LITTLE LLANO 014 2.0
END DESCRIPTION:
XS GIS Cut Line= 3
      2829655.65     10229853.14      2829417.50     10230061.00
      2829305.67     10230103.12
#Sta/Elev= 30
  4683.9 1095.74  4687.2 1095.74  4691.0 1094.63  4768.8 1089.55  4776.4 1088.06
  4798.7 1085.74  4840.0 1082.94  4860.9 1082.35  4868.5 1081.72  4932.1 1079.95
  4938.7 1080.08  4953.0 1078.66  4960.6 1078.36  4967.2 1078.65  4974.8 1077.04
  4980.7 1077.44  4995.7 1074.76  4995.9 1073.84  4996.1 1073.34  4999.6 1073.34
  4999.9 1073.84  5003.6 1073.84  5019.1 1076.87  5049.3 1080.05  5055.4 1081.14
  5087.4 1083.76  5098.1 1084.06  5104.4 1084.88  5109.7 1084.62  5119.5 1085.22
#Mann=5,-1,0
  4683.9    0.05       0  4798.7    0.12       0  4980.7    0.05       0
  4995.9    0.05       0  4999.9    0.05       0
Bank Sta=4995.9,4999.9
Exp/Cntr=0.3,0.1

Type RM Length L Ch R = 1,532,0,0,0
BEGIN DESCRIPTION:
LITTLE LLANO 014 1.0
END DESCRIPTION:
XS GIS Cut Line= 3
      2829555.72     10229803.11      2829384.75     10229800.00
      2829205.66     10229853.12
#Sta/Elev= 30
  4829.0 1088.61  4831.5 1088.61  4849.0 1087.02  4868.8 1084.17  4889.0 1082.42
  4909.1 1080.37  4929.1 1079.67  4949.1 1077.83  4959.1 1077.84  4967.5 1076.87
  4969.1 1076.68  4987.1 1070.40  4987.3 1069.90  4990.8 1069.90  4991.1 1070.40
  4997.0 1072.43  5002.1 1072.43  5009.5 1074.05  5040.7 1075.75  5069.1 1075.97
  5070.0 1076.00  5082.5 1076.43  5092.9 1077.31  5098.5 1078.86  5103.7 1078.37
  5131.7 1081.17  5145.1 1081.53  5164.9 1083.05  5170.2 1083.11  5186.8 1084.08
#Mann=7,-1,0
  4829.0    0.05       0  4868.8    0.12       0  4967.5    0.05       0
  4987.1    0.05       0  4991.1    0.05       0  5069.1    0.12       0
  5070.0    0.05       0
Bank Sta=4987.1,4991.1
Exp/Cntr=0.3,0.1

Chan Stop Cuts=-1