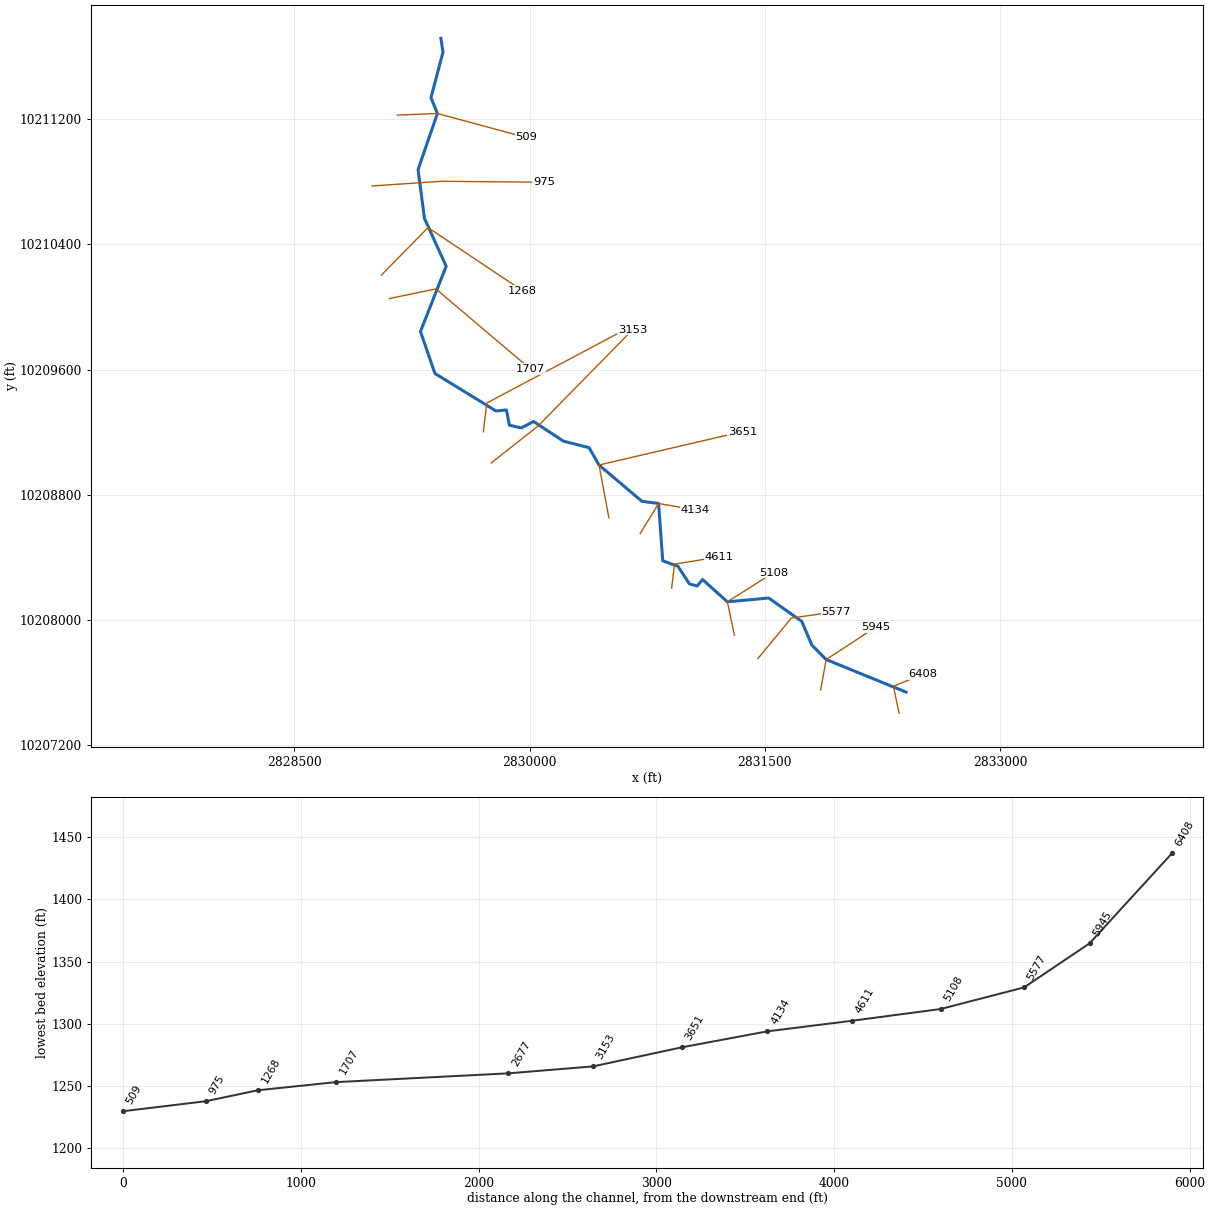
--- LITTLE LLANO 021.prj (project) ---

Proj Title=LITTLE LLANO 021 Base Level Engineering
Current Plan=p01
Default Exp/Contr=0.3,0.1
English Units
Geom File=g01
Flow File=f01
Plan File=p01
BEGIN DESCRIPTION:
LITTLE LLANO 021
END DESCRIPTION:

--- LITTLE LLANO 021.p01 (plan) ---

Plan Title=Multiple Run
Short Identifier=Multiple
Geom File=g01
Flow File=f01
Subcritical Flow
K Sum by GR= 0
Std Step Tol= 0.01
Critical Tol= 0.01
Num of Std Step Trials= 20
Max Error Tol= 0.3
Flow Tol Ratio= 0.001
Split Flow NTrial= 30
Split Flow Tol= 0.02
Split Flow Ratio= 0.02
Log Output Level= 0
Friction Slope Method= 1
Unsteady Friction Slope Method= 2
Unsteady Bridges Friction Slope Method= 1
Parabolic Critical Depth
Global Vel Dist=  1 , 1 , 1
Global Log Level= 0
CheckData=True
Encroach Param= -1, 0, 0, 0
BEGIN DESCRIPTION:
Multiple Run
END DESCRIPTION:

--- LITTLE LLANO 021.f01 (steady flow) ---

Flow Title=Multiple
Number of Profiles=7
Profile Names=10-year,25-year,50-year,1pct_min,100-year,1pct_plu,500-year
River Rch & RM= LITTLE LLANO 021,Reach-1,6408
      31      41      55      25      76     230     170
Boundary for River Rch & Prof#=LITTLE LLANO 021,Reach-1,1
Up Type=0
Dn Type=3
Dn Slope=0.005
Boundary for River Rch & Prof#=LITTLE LLANO 021,Reach-1,2
Up Type=0
Dn Type=3
Dn Slope=0.005
Boundary for River Rch & Prof#=LITTLE LLANO 021,Reach-1,3
Up Type=0
Dn Type=3
Dn Slope=0.005
Boundary for River Rch & Prof#=LITTLE LLANO 021,Reach-1,4
Up Type=0
Dn Type=3
Dn Slope=0.005
Boundary for River Rch & Prof#=LITTLE LLANO 021,Reach-1,5
Up Type=0
Dn Type=3
Dn Slope=0.005
Boundary for River Rch & Prof#=LITTLE LLANO 021,Reach-1,6
Up Type=0
Dn Type=3
Dn Slope=0.005
Boundary for River Rch & Prof#=LITTLE LLANO 021,Reach-1,7
Up Type=0
Dn Type=3
Dn Slope=0.005

--- LITTLE LLANO 021.g01 (geometry) ---

Geom Title=Existing Conditions

River Reach=LITTLE LLANO 021,Reach-1
Reach XY= 30
      2832400.00     10207539.00      2831890.75     10207747.00
      2831799.25     10207840.00      2831735.00     10207991.00
      2831524.75     10208140.00      2831261.00     10208116.00
      2831103.00     10208258.00      2831068.25     10208217.00
      2831019.50     10208230.00      2830945.75     10208343.00
      2830849.00     10208378.00      2830822.75     10208744.00
      2830716.50     10208758.00      2830442.75     10208990.00
      2830379.50     10209101.00      2830216.50     10209142.00
      2830025.50     10209268.00      2829948.00     10209227.00
      2829871.75     10209244.00      2829852.25     10209342.00
      2829786.25     10209335.00      2829396.75     10209575.00
      2829304.75     10209843.00      2829468.50     10210260.00
      2829330.00     10210566.00      2829289.50     10210877.00
      2829412.75     10211236.00      2829371.75     10211337.00
      2829448.25     10211628.00      2829435.00     10211716.00

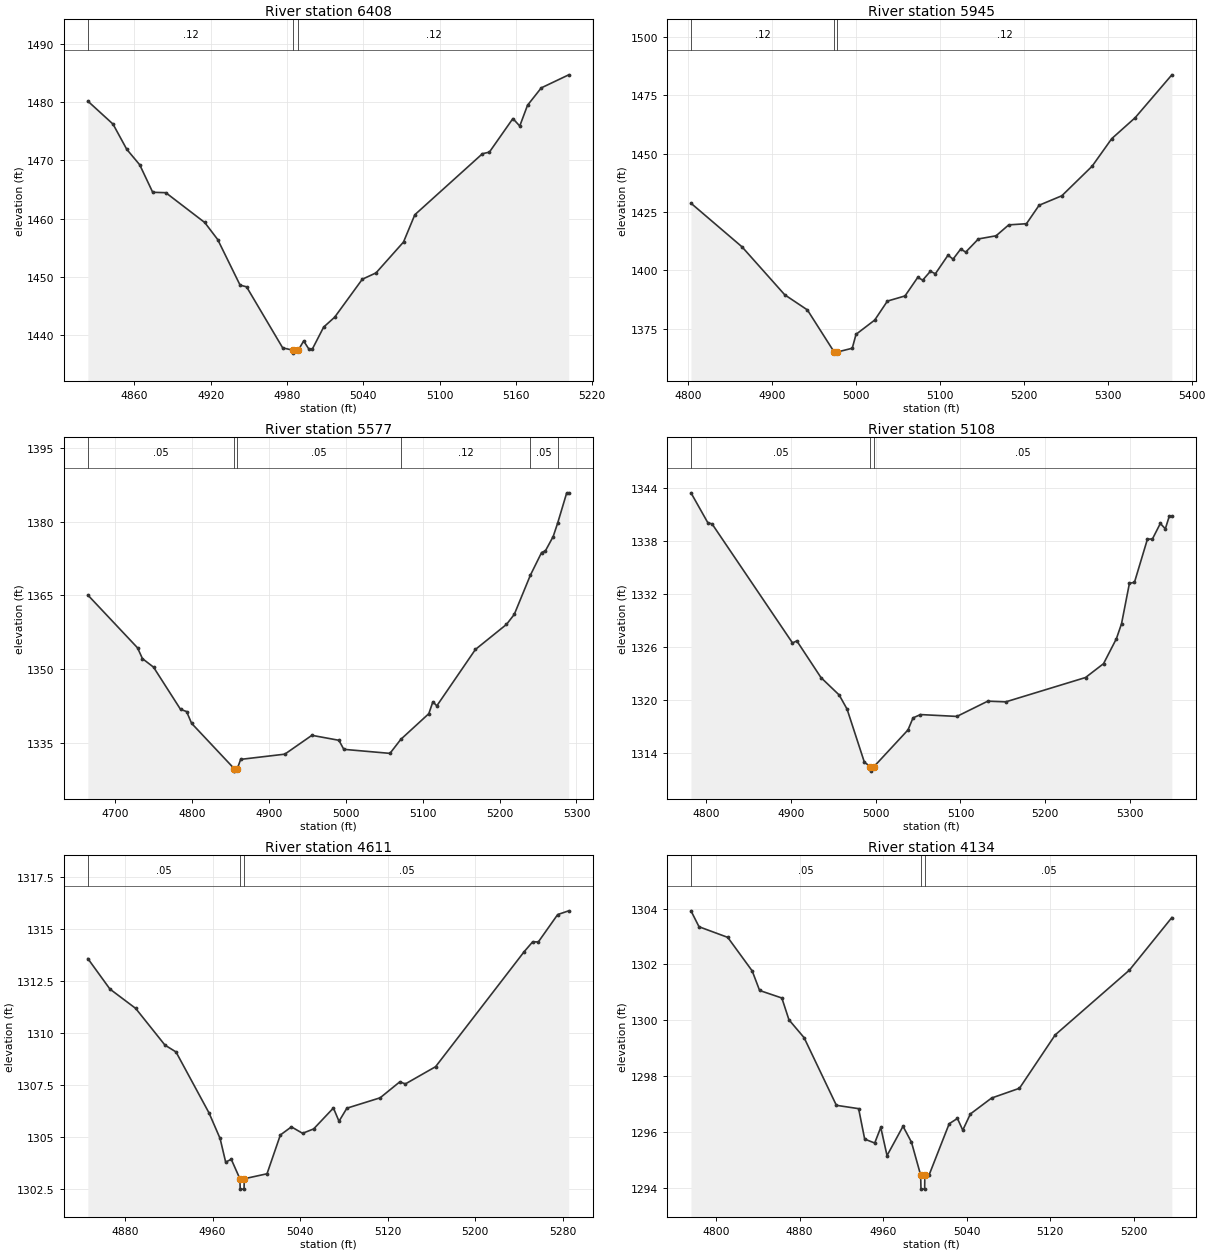
Type RM Length L Ch R = 1,6408,463,463,463
BEGIN DESCRIPTION:
LITTLE LLANO 021 12.0
END DESCRIPTION:
XS GIS Cut Line= 3
      2832355.68     10207403.15      2832319.50     10207576.00
      2832505.66     10207653.10
#Sta/Elev= 30
  4823.4 1480.17  4843.2 1476.23  4854.0 1471.91  4864.2 1469.25  4874.4 1464.54
  4884.7 1464.47  4915.3 1459.36  4925.5 1456.44  4943.1 1448.62  4948.2 1448.33
  4976.6 1437.86  4984.8 1437.46  4985.1 1436.96  4988.8 1437.46  4993.1 1439.04
  4997.1 1437.69  5000.0 1437.69  5008.8 1441.42  5017.5 1443.13  5039.2 1449.63
  5050.0 1450.72  5071.6 1456.01  5080.5 1460.69  5133.7 1471.16  5139.1 1471.42
  5157.6 1477.18  5163.0 1475.90  5169.1 1479.46  5179.9 1482.44  5201.5 1484.68
#Mann=3,-1,0
  4823.4    0.12       0  4984.8    0.07       0  4988.8    0.12       0
Bank Sta=4984.8,4988.8
Exp/Cntr=0.3,0.1

Type RM Length L Ch R = 1,5945,368,368,368
BEGIN DESCRIPTION:
LITTLE LLANO 021 11.0
END DESCRIPTION:
XS GIS Cut Line= 3
      2831855.69     10207553.14      2831890.75     10207747.00
      2832205.70     10207953.12
#Sta/Elev= 30
  4803.0 1428.75  4863.9 1410.08  4914.8 1389.58  4941.8 1383.11  4973.7 1365.13
  4974.0 1364.63  4977.7 1365.13  4995.3 1366.72  4999.8 1372.67  5022.1 1378.78
  5037.2 1386.89  5058.2 1389.09  5073.4 1397.03  5079.3 1395.86  5088.5 1399.64
  5094.4 1398.58  5109.5 1406.53  5115.5 1404.83  5124.6 1409.15  5130.6 1407.85
  5145.7 1413.47  5166.8 1414.82  5181.9 1419.49  5203.0 1419.98  5218.1 1427.88
  5245.2 1431.94  5281.3 1444.58  5304.7 1456.37  5332.6 1465.32  5376.4 1483.67
#Mann=3,-1,0
  4803.0    0.12       0  4973.7    0.07       0  4977.7    0.12       0
Bank Sta=4973.7,4977.7
Exp/Cntr=0.3,0.1

Type RM Length L Ch R = 1,5577,469,469,469
BEGIN DESCRIPTION:
LITTLE LLANO 021 10.0
END DESCRIPTION:
XS GIS Cut Line= 3
      2831455.68     10207753.10      2831668.75     10208012.00
      2831955.72     10208053.12
#Sta/Elev= 30
  4664.7 1365.05  4729.3 1354.32  4735.7 1352.12  4750.1 1350.39  4785.2 1341.81
  4793.1 1341.36  4799.6 1338.97  4855.0 1329.75  4855.2 1329.25  4859.0 1329.75
  4863.4 1331.64  4920.8 1332.70  4956.0 1336.53  4991.1 1335.52  4997.5 1333.68
  5057.5 1332.86  5071.6 1335.71  5108.0 1340.93  5113.3 1343.35  5118.4 1342.52
  5168.6 1353.99  5209.0 1359.08  5219.1 1361.11  5240.0 1369.07  5254.6 1373.69
  5259.6 1374.04  5269.7 1376.95  5275.5 1379.67  5287.3 1385.83  5289.9 1385.83
#Mann=6,-1,0
  4664.7    0.05       0  4855.0    0.05       0  4859.0    0.05       0
  5071.6    0.12       0  5240.0    0.05       0  5275.5    0.12       0
Bank Sta=4855,4859
Exp/Cntr=0.3,0.1

Type RM Length L Ch R = 1,5108,497,497,497
BEGIN DESCRIPTION:
LITTLE LLANO 021 9.0
END DESCRIPTION:
XS GIS Cut Line= 3
      2831305.68     10207903.14      2831261.00     10208116.00
      2831555.71     10208303.13
#Sta/Elev= 30
  4782.5 1343.43  4802.3 1340.05  4807.4 1339.90  4902.1 1326.42  4907.2 1326.65
  4935.7 1322.49  4957.1 1320.52  4966.4 1318.92  4986.8 1312.90  4994.0 1312.39
  4994.2 1311.89  4998.0 1312.39  5038.2 1316.56  5044.1 1317.92  5052.9 1318.30
  5095.8 1318.09  5132.2 1319.82  5153.4 1319.74  5247.4 1322.50  5268.6 1324.07
  5283.8 1326.91  5289.8 1328.60  5299.1 1333.18  5305.0 1333.28  5320.3 1338.18
  5326.2 1338.20  5335.5 1339.96  5341.4 1339.35  5346.1 1340.80  5349.1 1340.80
#Mann=3,-1,0
  4782.5    0.05       0  4994.0    0.03       0  4998.0    0.05       0
Bank Sta=4994,4998
Exp/Cntr=0.3,0.1

Type RM Length L Ch R = 1,4611,477,477,477
BEGIN DESCRIPTION:
LITTLE LLANO 021 8.0
END DESCRIPTION:
XS GIS Cut Line= 3
      2830905.68     10208203.09      2830924.00     10208356.00
      2831205.69     10208403.11
#Sta/Elev= 30
  4846.0 1313.58  4866.2 1312.11  4889.7 1311.18  4916.5 1309.41  4926.6 1309.08
  4956.8 1306.14  4966.9 1304.91  4972.0 1303.77  4977.1 1303.91  4985.0 1302.97
  4985.3 1302.47  4988.8 1302.47  4989.0 1302.97  5009.8 1303.21  5022.0 1305.08
  5032.1 1305.47  5042.3 1305.16  5052.4 1305.37  5070.5 1306.38  5075.6 1305.74
  5082.8 1306.37  5113.2 1306.87  5131.2 1307.64  5136.3 1307.54  5163.9 1308.37
  5245.0 1313.92  5252.7 1314.39  5257.8 1314.38  5275.5 1315.70  5285.6 1315.88
#Mann=3,-1,0
  4846.0    0.05       0  4985.0    0.05       0  4989.0    0.05       0
Bank Sta=4985,4989
Exp/Cntr=0.3,0.1

Type RM Length L Ch R = 1,4134,483,483,483
BEGIN DESCRIPTION:
LITTLE LLANO 021 7.0
END DESCRIPTION:
XS GIS Cut Line= 3
      2830705.70     10208553.13      2830822.75     10208744.00
      2831055.69     10208703.11
#Sta/Elev= 30
  4776.1 1303.92  4783.8 1303.35  4811.3 1302.97  4834.7 1301.77  4841.8 1301.07
  4863.1 1300.80  4869.9 1300.02  4884.4 1299.38  4915.3 1296.96  4936.6 1296.84
  4942.4 1295.75  4952.0 1295.61  4957.8 1296.17  4963.8 1295.16  4979.1 1296.21
  4987.2 1295.64  4996.0 1294.46  4996.3 1293.96  4999.8 1293.96  5000.0 1294.46
  5004.0 1294.46  5023.3 1296.30  5031.2 1296.49  5036.3 1296.07  5043.6 1296.65
  5063.9 1297.22  5090.6 1297.57  5124.8 1299.48  5195.9 1301.80  5236.5 1303.68
#Mann=3,-1,0
  4776.1    0.05       0  4996.0    0.05       0  5000.0    0.05       0
Bank Sta=4996,5000
Exp/Cntr=0.3,0.1

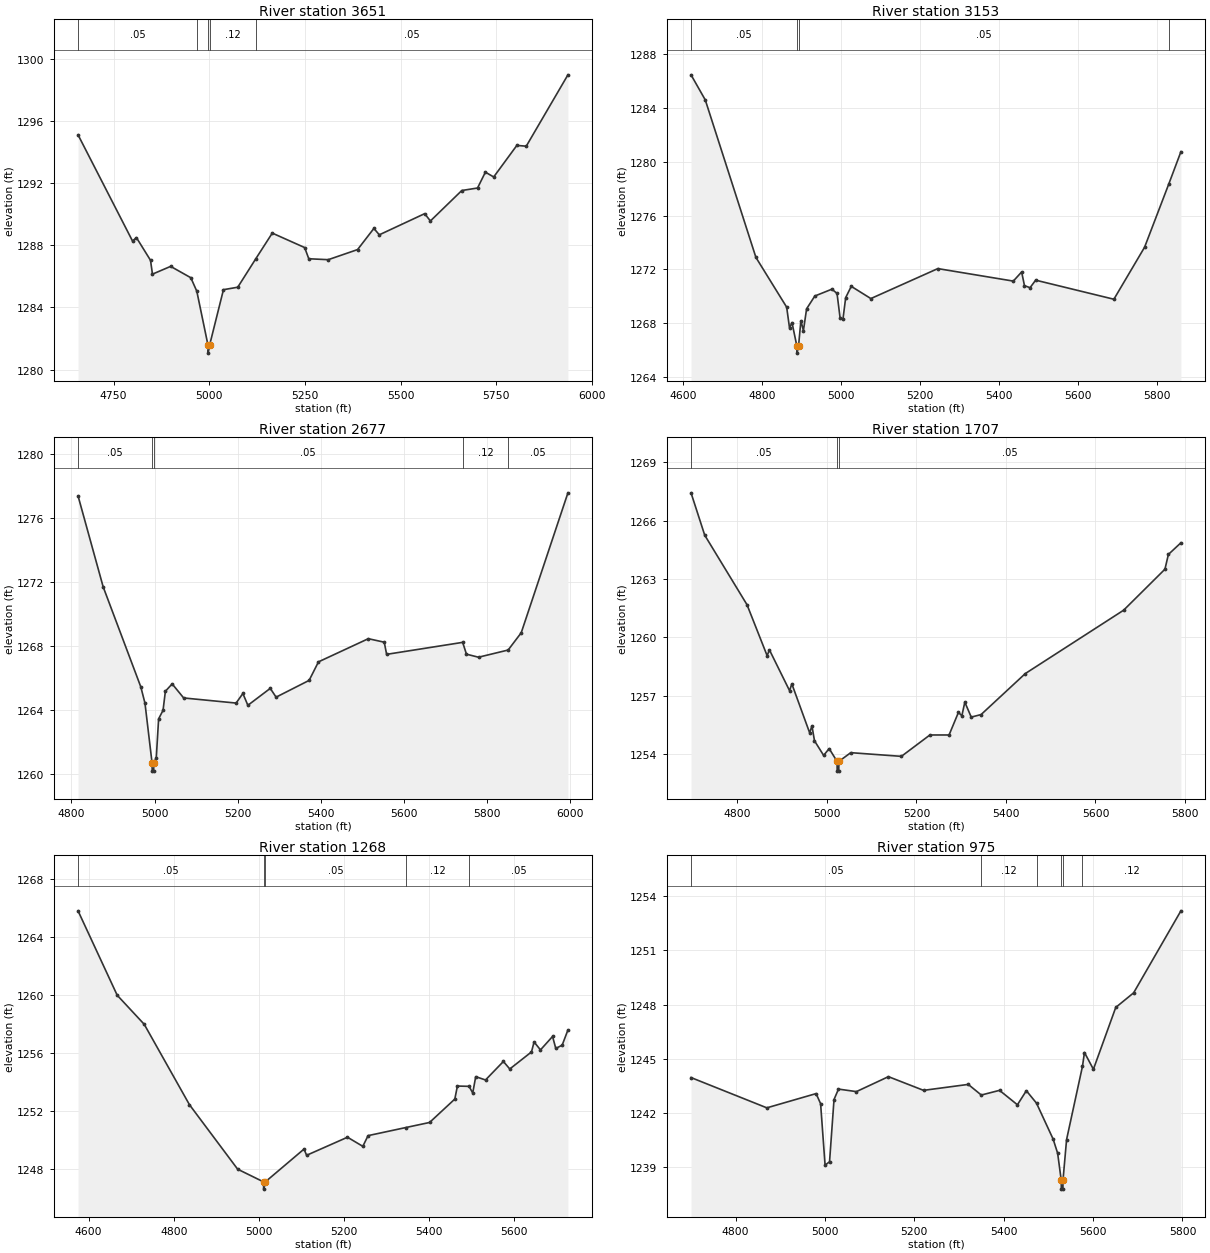
Type RM Length L Ch R = 1,3651,498,498,498
BEGIN DESCRIPTION:
LITTLE LLANO 021 6.0
END DESCRIPTION:
XS GIS Cut Line= 3
      2830505.68     10208653.13      2830442.75     10208990.00
      2831355.71     10209203.12
#Sta/Elev= 30
  4657.3 1295.10  4799.7 1288.27  4809.9 1288.49  4846.7 1287.03  4851.8 1286.14
  4899.3 1286.64  4952.0 1285.91  4967.7 1285.04  4997.0 1281.56  4997.3 1281.06
  5001.0 1281.56  5037.3 1285.14  5074.7 1285.30  5121.3 1287.11  5164.9 1288.78
  5249.5 1287.85  5260.3 1287.13  5311.1 1287.07  5387.8 1287.72  5430.4 1289.08
  5444.6 1288.67  5563.1 1290.03  5578.1 1289.56  5660.2 1291.52  5701.3 1291.68
  5721.8 1292.70  5743.5 1292.39  5804.0 1294.42  5828.6 1294.37  5937.5 1298.96
#Mann=5,-1,0
  4657.3    0.05       0  4967.7    0.12       0  4997.0    0.07       0
  5001.0    0.12       0  5121.3    0.05       0
Bank Sta=4997,5001
Exp/Cntr=0.3,0.1

Type RM Length L Ch R = 1,3153,476,476,476
BEGIN DESCRIPTION:
LITTLE LLANO 021 5.0
END DESCRIPTION:
XS GIS Cut Line= 3
      2829755.69     10209003.11      2830053.00     10209238.00
      2830655.71     10209853.14
#Sta/Elev= 30
  4621.1 1286.47  4657.2 1284.60  4785.4 1272.88  4863.2 1269.18  4870.4 1267.64
  4876.7 1268.03  4889.2 1266.26  4889.4 1265.76  4893.2 1266.26  4899.2 1268.17
  4905.6 1267.44  4913.7 1269.06  4934.5 1270.01  4977.8 1270.52  4990.7 1270.20
  4998.5 1268.37  5005.6 1268.27  5012.6 1269.89  5026.7 1270.73  5076.3 1269.82
  5245.9 1272.05  5436.9 1271.12  5458.0 1271.80  5465.2 1270.78  5479.3 1270.63
  5493.5 1271.19  5691.5 1269.77  5769.2 1273.64  5830.4 1278.34  5861.2 1280.75
#Mann=4,-1,0
  4621.1    0.05       0  4889.2    0.03       0  4893.2    0.05       0
  5830.4    0.12       0
Bank Sta=4889.2,4893.2
Exp/Cntr=0.3,0.1

Type RM Length L Ch R = 1,2677,970,970,970
BEGIN DESCRIPTION:
LITTLE LLANO 021 4.0
END DESCRIPTION:
XS GIS Cut Line= 3
      2829705.68     10209203.10      2829727.50     10209386.00
      2830605.70     10209853.12
#Sta/Elev= 30
  4815.8 1277.41  4876.2 1271.72  4966.9 1265.45  4976.9 1264.43  4994.0 1260.68
  4994.3 1260.18  4997.8 1260.18  4998.0 1260.68  5004.1 1261.02  5009.7 1263.45
  5020.4 1263.99  5026.0 1265.18  5042.3 1265.64  5070.0 1264.76  5196.2 1264.44
  5212.5 1265.04  5224.5 1264.30  5278.4 1265.36  5292.4 1264.81  5371.9 1265.86
  5394.4 1267.02  5514.4 1268.47  5552.7 1268.25  5558.4 1267.49  5741.4 1268.24
  5750.5 1267.50  5779.5 1267.31  5850.8 1267.76  5882.3 1268.84  5994.7 1277.60
#Mann=5,-1,0
  4815.8    0.05       0  4994.0    0.05       0  4998.0    0.05       0
  5741.4    0.12       0  5850.8    0.05       0
Bank Sta=4994,4998
Exp/Cntr=0.3,0.1

Type RM Length L Ch R = 1,1707,439,439,439
BEGIN DESCRIPTION:
LITTLE LLANO 021 3.0
END DESCRIPTION:
XS GIS Cut Line= 3
      2829105.73     10210053.12      2829402.75     10210115.00
      2830005.67     10209603.13
#Sta/Elev= 30
  4696.6 1267.43  4727.2 1265.25  4821.7 1261.67  4866.6 1259.05  4871.7 1259.35
  4916.7 1257.25  4921.8 1257.60  4961.6 1255.08  4966.7 1255.44  4972.4 1254.67
  4992.8 1253.92  5005.2 1254.27  5022.8 1253.61  5023.1 1253.11  5026.6 1253.11
  5026.8 1253.61  5053.4 1254.06  5166.5 1253.87  5230.2 1254.97  5273.0 1254.97
  5293.9 1256.13  5301.6 1255.96  5308.2 1256.66  5322.5 1255.89  5344.5 1256.02
  5443.3 1258.13  5662.9 1261.39  5755.2 1263.50  5762.9 1264.26  5790.9 1264.86
#Mann=3,-1,0
  4696.6    0.05       0  5022.8    0.03       0  5026.8    0.05       0
Bank Sta=5022.8,5026.8
Exp/Cntr=0.3,0.1

Type RM Length L Ch R = 1,1268,293,293,293
BEGIN DESCRIPTION:
LITTLE LLANO 021 2.0
END DESCRIPTION:
XS GIS Cut Line= 3
      2829055.66     10210203.09      2829352.75     10210507.00
      2829955.68     10210103.12
#Sta/Elev= 30
  4575.0 1265.83  4667.0 1259.99  4730.5 1257.98  4836.7 1252.42  4949.9 1247.96
  5010.8 1247.08  5011.0 1246.58  5014.8 1247.08  5105.8 1249.35  5111.9 1248.92
  5207.9 1250.17  5243.9 1249.54  5256.3 1250.28  5344.9 1250.84  5400.7 1251.19
  5460.0 1252.81  5466.1 1253.71  5493.4 1253.69  5502.1 1253.23  5509.1 1254.36
  5532.1 1254.13  5574.1 1255.41  5589.1 1254.89  5640.1 1256.07  5646.2 1256.76
  5661.2 1256.21  5689.6 1257.14  5697.2 1256.31  5712.2 1256.54  5725.7 1257.59
#Mann=5,-1,0
  4575.0    0.05       0  5010.8    0.03       0  5014.8    0.05       0
  5344.9    0.12       0  5493.4    0.05       0
Bank Sta=5010.8,5014.8
Exp/Cntr=0.3,0.1

Type RM Length L Ch R = 1,975,466,466,466
BEGIN DESCRIPTION:
Mapping XS a4cff859
END DESCRIPTION:
XS GIS Cut Line= 3
      2828996.49     10210772.80      2829437.13     10210802.58
      2830091.46     10210796.63
#Sta/Elev= 30
  4700.5 1243.95  4870.1 1242.27  4980.3 1243.06  4990.4 1242.50  5000.4 1239.09
  5010.4 1239.28  5020.4 1242.73  5030.4 1243.31  5070.5 1243.17  5142.1 1244.00
  5220.7 1243.24  5320.7 1243.57  5349.9 1242.98  5390.7 1243.24  5430.7 1242.44
  5450.7 1243.22  5473.4 1242.53  5510.7 1240.53  5520.7 1239.75  5528.7 1238.26
  5529.0 1237.76  5532.5 1237.76  5532.7 1238.26  5540.7 1240.51  5576.3 1244.58
  5580.7 1245.34  5600.7 1244.41  5650.7 1247.84  5690.7 1248.65  5796.5 1253.20
#Mann=6,-1,0
  4700.5    0.05       0  5349.9    0.12       0  5473.4    0.05       0
  5528.7    0.03       0  5532.7    0.05       0  5576.3    0.12       0
Bank Sta=5528.7,5532.7
Exp/Cntr=0.3,0.1

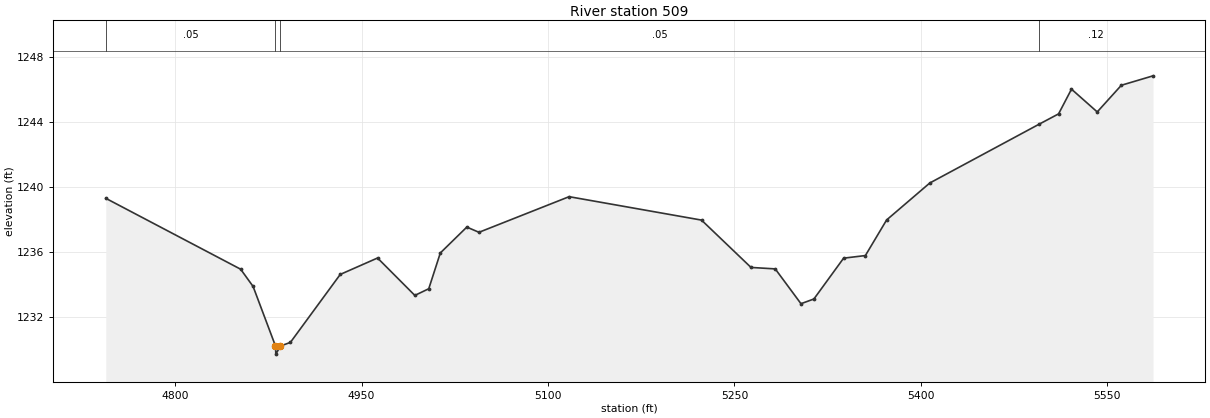
Type RM Length L Ch R = 1,509,0,0,0
BEGIN DESCRIPTION:
LITTLE LLANO 021 1.0
END DESCRIPTION:
XS GIS Cut Line= 3
      2829157.27     10211225.36      2829412.75     10211236.00
      2829979.00     10211082.45
#Sta/Elev= 30
  4744.3 1239.30  4852.8 1234.94  4862.8 1233.88  4880.8 1230.22  4881.1 1229.72
  4884.8 1230.22  4892.8 1230.44  4932.9 1234.62  4962.9 1235.63  4992.9 1233.33
  5004.1 1233.74  5013.4 1235.94  5034.7 1237.53  5044.5 1237.21  5117.0 1239.40
  5223.5 1237.96  5263.3 1235.05  5282.8 1234.96  5303.5 1232.82  5313.9 1233.11
  5337.8 1235.62  5355.3 1235.78  5372.4 1237.97  5407.1 1240.24  5494.9 1243.85
  5510.7 1244.49  5521.1 1246.01  5541.8 1244.61  5561.2 1246.25  5586.7 1246.83
#Mann=4,-1,0
  4744.3    0.05       0  4880.8    0.05       0  4884.8    0.05       0
  5494.9    0.12       0
Bank Sta=4880.8,4884.8
Exp/Cntr=0.3,0.1

Chan Stop Cuts=-1