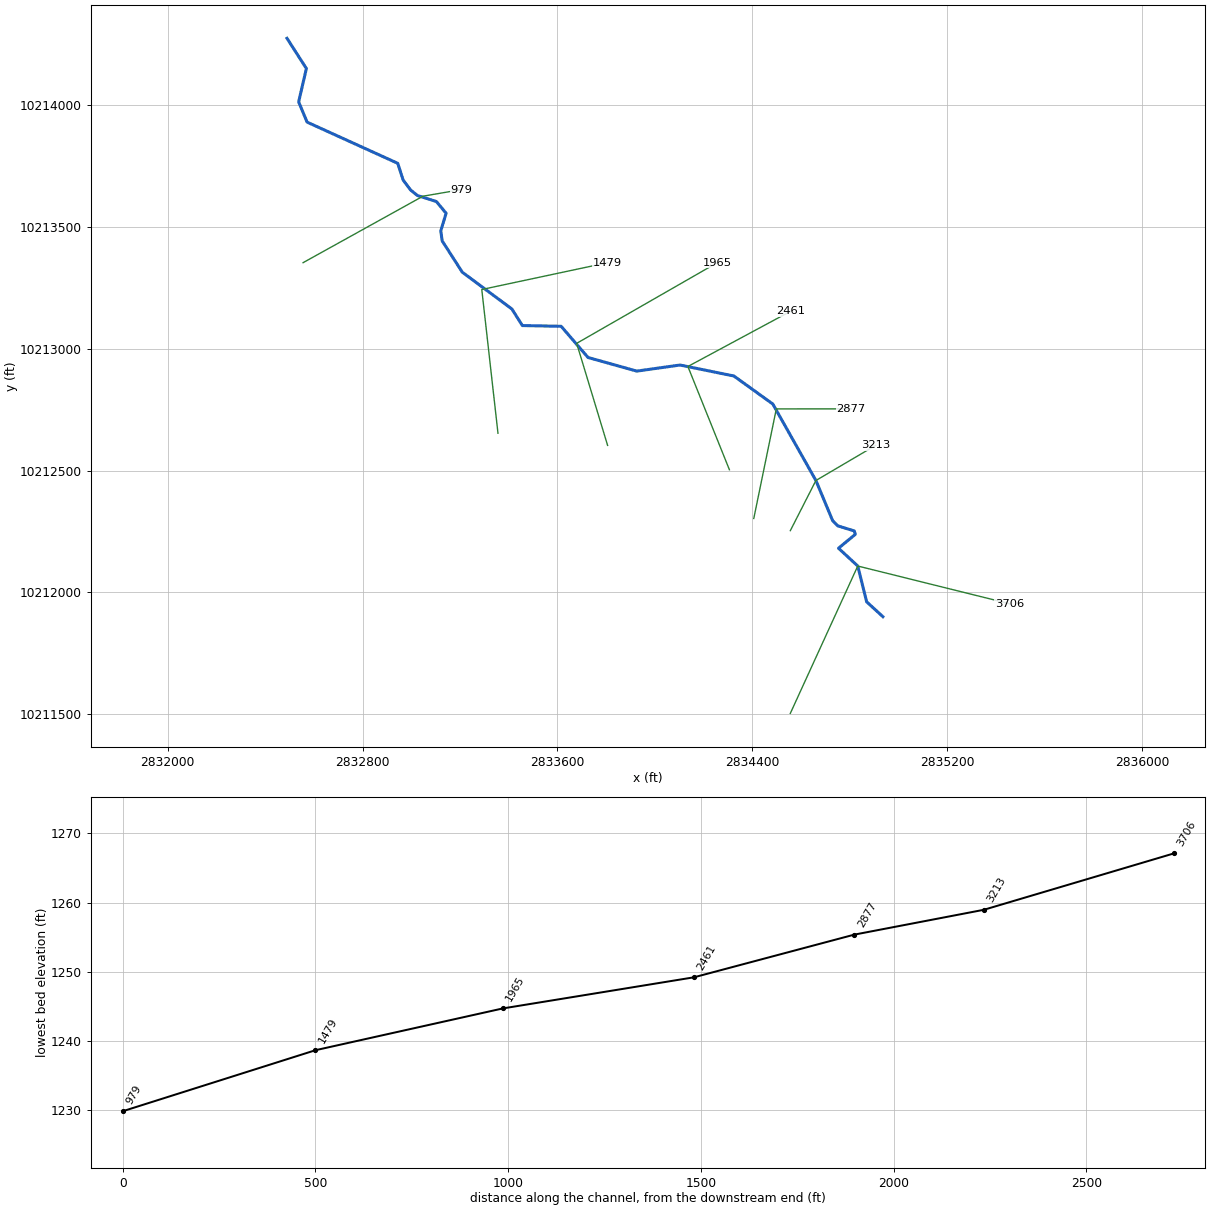
--- LITTLE LLANO 023.prj (project) ---

Proj Title=LITTLE LLANO 023 Base Level Engineering
Current Plan=p01
Default Exp/Contr=0.3,0.1
English Units
Geom File=g01
Flow File=f01
Plan File=p01
BEGIN DESCRIPTION:
LITTLE LLANO 023
END DESCRIPTION:

--- LITTLE LLANO 023.p01 (plan) ---

Plan Title=Multiple Run
Short Identifier=Multiple
Geom File=g01
Flow File=f01
Subcritical Flow
K Sum by GR= 0
Std Step Tol= 0.01
Critical Tol= 0.01
Num of Std Step Trials= 20
Max Error Tol= 0.3
Flow Tol Ratio= 0.001
Split Flow NTrial= 30
Split Flow Tol= 0.02
Split Flow Ratio= 0.02
Log Output Level= 0
Friction Slope Method= 1
Unsteady Friction Slope Method= 2
Unsteady Bridges Friction Slope Method= 1
Parabolic Critical Depth
Global Vel Dist=  1 , 1 , 1
Global Log Level= 0
CheckData=True
Encroach Param= -1, 0, 0, 0
BEGIN DESCRIPTION:
Multiple Run
END DESCRIPTION:

--- LITTLE LLANO 023.f01 (steady flow) ---

Flow Title=Multiple
Number of Profiles=7
Profile Names=10-year,25-year,50-year,1pct_min,100-year,1pct_plu,500-year
River Rch & RM= LITTLE LLANO 023,Reach-1,3706
      37      55      77      37     112     338     264
Boundary for River Rch & Prof#=LITTLE LLANO 023,Reach-1,1
Up Type=0
Dn Type=3
Dn Slope=0.005
Boundary for River Rch & Prof#=LITTLE LLANO 023,Reach-1,2
Up Type=0
Dn Type=3
Dn Slope=0.005
Boundary for River Rch & Prof#=LITTLE LLANO 023,Reach-1,3
Up Type=0
Dn Type=3
Dn Slope=0.005
Boundary for River Rch & Prof#=LITTLE LLANO 023,Reach-1,4
Up Type=0
Dn Type=3
Dn Slope=0.005
Boundary for River Rch & Prof#=LITTLE LLANO 023,Reach-1,5
Up Type=0
Dn Type=3
Dn Slope=0.005
Boundary for River Rch & Prof#=LITTLE LLANO 023,Reach-1,6
Up Type=0
Dn Type=3
Dn Slope=0.005
Boundary for River Rch & Prof#=LITTLE LLANO 023,Reach-1,7
Up Type=0
Dn Type=3
Dn Slope=0.005

--- LITTLE LLANO 023.g01 (geometry) ---

Geom Title=Existing Conditions

River Reach=LITTLE LLANO 023,Reach-1
Reach XY= 30
      2834935.75     10211900.00      2834869.00     10211961.00
      2834832.50     10212108.00      2834753.50     10212181.00
      2834822.50     10212238.00      2834818.25     10212252.00
      2834750.00     10212273.00      2834729.50     10212294.00
      2834660.75     10212459.00      2834483.75     10212773.00
      2834324.00     10212888.00      2834103.00     10212933.00
      2833925.50     10212908.00      2833725.25     10212964.00
      2833615.00     10213092.00      2833455.75     10213095.00
      2833412.75     10213163.00      2833209.25     10213314.00
      2833127.00     10213442.00      2833120.75     10213483.00
      2833142.75     10213556.00      2833103.00     10213604.00
      2833024.75     10213629.00      2832996.50     10213652.00
      2832966.50     10213692.00      2832944.25     10213761.00
      2832572.25     10213930.00      2832537.50     10214013.00
      2832569.25     10214150.00      2832489.75     10214274.00

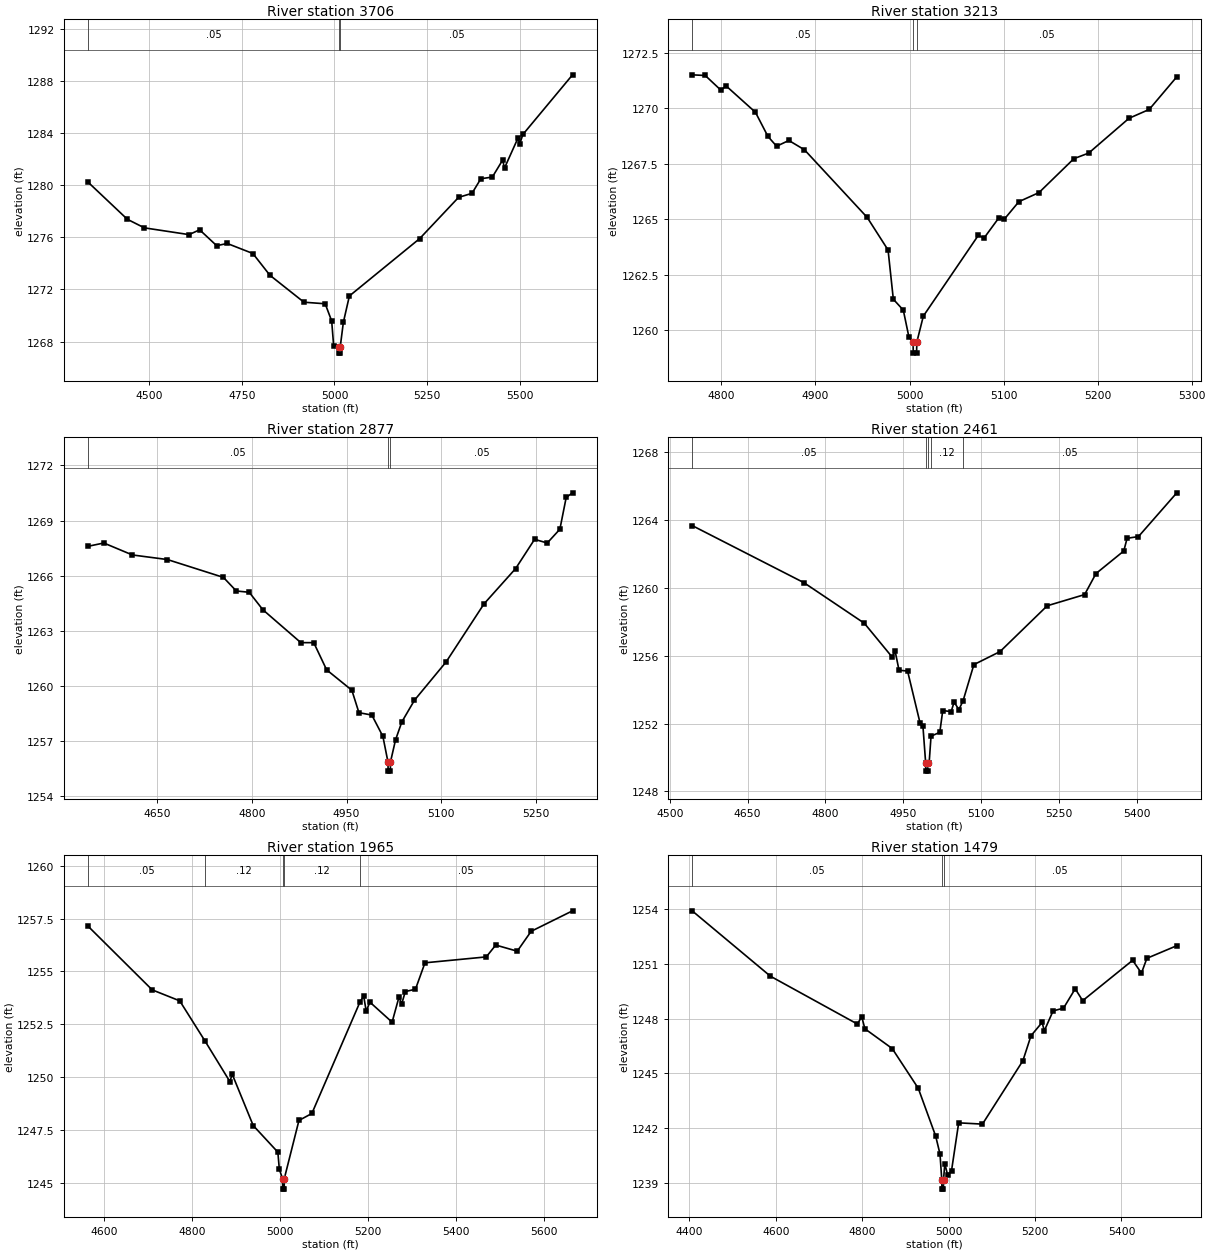
Type RM Length L Ch R = 1,3706,493,493,493
BEGIN DESCRIPTION:
LITTLE LLANO 023 7.0
END DESCRIPTION:
XS GIS Cut Line= 3
      2834555.69     10211503.13      2834832.50     10212108.00
      2835455.64     10211953.12
#Sta/Elev= 30
  4334.8 1280.25  4441.1 1277.39  4487.1 1276.73  4607.7 1276.21  4636.2 1276.58
  4682.2 1275.36  4710.7 1275.53  4779.8 1274.76  4825.8 1273.09  4917.6 1271.02
  4974.9 1270.90  4992.4 1269.58  4997.8 1267.66  5011.6 1267.61  5011.8 1267.11
  5015.3 1267.11  5015.6 1267.61  5023.9 1269.47  5040.2 1271.50  5230.0 1275.91
  5334.7 1279.07  5370.9 1279.38  5394.8 1280.50  5425.8 1280.63  5453.5 1281.93
  5458.7 1281.33  5494.9 1283.62  5500.0 1283.20  5508.2 1283.90  5642.1 1288.48
#Mann=3,-1,0
  4334.8    0.05       0  5011.6    0.03       0  5015.6    0.05       0
Bank Sta=5011.6,5015.6
Exp/Cntr=0.3,0.1

Type RM Length L Ch R = 1,3213,336,336,336
BEGIN DESCRIPTION:
LITTLE LLANO 023 6.0
END DESCRIPTION:
XS GIS Cut Line= 3
      2834555.71     10212253.15      2834660.75     10212459.00
      2834905.70     10212603.12
#Sta/Elev= 30
  4768.9 1271.51  4782.8 1271.48  4799.4 1270.82  4805.0 1271.01  4836.2 1269.82
  4849.5 1268.73  4858.7 1268.29  4871.7 1268.55  4888.3 1268.13  4955.0 1265.08
  4977.2 1263.61  4982.8 1261.39  4993.4 1260.90  4999.4 1259.68  5003.8 1259.46
  5004.0 1258.96  5007.5 1258.96  5007.8 1259.46  5014.7 1260.63  5073.3 1264.28
  5079.1 1264.14  5094.8 1265.05  5100.6 1264.99  5116.3 1265.79  5137.7 1266.20
  5174.8 1267.73  5190.5 1267.98  5233.4 1269.55  5254.9 1269.95  5284.2 1271.42
#Mann=3,-1,0
  4768.9    0.05       0  5003.8    0.03       0  5007.8    0.05       0
Bank Sta=5003.8,5007.8
Exp/Cntr=0.3,0.1

Type RM Length L Ch R = 1,2877,416,416,416
BEGIN DESCRIPTION:
LITTLE LLANO 023 5.0
END DESCRIPTION:
XS GIS Cut Line= 3
      2834405.69     10212303.12      2834498.25     10212753.00
      2834805.65     10212753.11
#Sta/Elev= 30
  4540.7 1267.60  4565.9 1267.78  4611.1 1267.13  4666.5 1266.88  4755.1 1265.91
  4775.5 1265.17  4795.9 1265.10  4817.5 1264.15  4877.6 1262.36  4898.0 1262.36
  4918.4 1260.88  4958.3 1259.77  4969.5 1258.55  4989.9 1258.42  5007.4 1257.26
  5015.4 1255.87  5015.7 1255.37  5019.2 1255.37  5019.4 1255.87  5027.4 1257.07
  5037.4 1258.05  5057.4 1259.23  5107.4 1261.31  5167.4 1264.47  5217.4 1266.39
  5247.4 1267.98  5267.4 1267.78  5287.4 1268.53  5297.4 1270.26  5307.4 1270.51
#Mann=3,-1,0
  4540.7    0.05       0  5015.4    0.05       0  5019.4    0.05       0
Bank Sta=5015.4,5019.4
Exp/Cntr=0.3,0.1

Type RM Length L Ch R = 1,2461,496,496,496
BEGIN DESCRIPTION:
LITTLE LLANO 023 4.0
END DESCRIPTION:
XS GIS Cut Line= 3
      2834305.70     10212503.08      2834135.25     10212927.00
      2834555.70     10213153.12
#Sta/Elev= 30
  4543.1 1263.68  4758.7 1260.31  4875.0 1257.92  4928.8 1255.92  4934.2 1256.30
  4941.9 1255.15  4958.4 1255.10  4982.5 1252.03  4987.9 1251.89  4993.2 1249.70
  4993.5 1249.20  4997.0 1249.20  4997.2 1249.70  5000.0 1249.70  5003.6 1251.26
  5020.5 1251.49  5026.2 1252.77  5042.4 1252.71  5048.1 1253.27  5057.3 1252.83
  5065.3 1253.34  5086.2 1255.48  5136.7 1256.25  5227.6 1258.95  5299.7 1259.61
  5321.6 1260.85  5375.2 1262.18  5381.6 1262.93  5403.5 1263.03  5477.4 1265.61
#Mann=5,-1,0
  4543.1    0.05       0  4993.2    0.05       0  4997.2    0.05       0
  5003.6    0.12       0  5065.3    0.05       0
Bank Sta=4993.2,4997.2
Exp/Cntr=0.3,0.1

Type RM Length L Ch R = 1,1965,486,486,486
BEGIN DESCRIPTION:
LITTLE LLANO 023 3.0
END DESCRIPTION:
XS GIS Cut Line= 3
      2833805.68     10212603.11      2833678.75     10213022.00
      2834255.69     10213353.11
#Sta/Elev= 30
  4562.3 1257.15  4708.6 1254.13  4771.3 1253.61  4829.4 1251.69  4885.4 1249.79
  4890.7 1250.14  4938.5 1247.71  4994.6 1246.45  4998.0 1245.63  5005.3 1245.20
  5005.5 1244.70  5009.0 1244.70  5009.3 1245.20  5042.6 1247.95  5072.0 1248.28
  5181.4 1253.55  5189.9 1253.84  5195.7 1253.12  5204.0 1253.55  5254.6 1252.60
  5270.4 1253.80  5276.2 1253.45  5284.7 1254.05  5307.8 1254.16  5329.4 1255.41
  5468.9 1255.69  5490.5 1256.25  5539.4 1255.96  5571.0 1256.90  5665.2 1257.87
#Mann=5,-1,0
  4562.3    0.05       0  4829.4    0.12       0  5005.3    0.07       0
  5009.3    0.12       0  5181.4    0.05       0
Bank Sta=5005.3,5009.3
Exp/Cntr=0.3,0.1

Type RM Length L Ch R = 1,1479,500,500,500
BEGIN DESCRIPTION:
LITTLE LLANO 023 2.0
END DESCRIPTION:
XS GIS Cut Line= 3
      2833355.68     10212653.13      2833289.25     10213243.00
      2833805.64     10213353.10
#Sta/Elev= 30
  4406.4 1253.90  4587.5 1250.32  4788.8 1247.70  4798.8 1248.10  4806.2 1247.44
  4869.3 1246.36  4929.7 1244.18  4969.9 1241.57  4980.0 1240.58  4984.1 1239.16
  4984.4 1238.66  4987.9 1238.66  4988.1 1239.16  4991.1 1240.05  4997.5 1239.45
  5006.6 1239.66  5023.2 1242.29  5078.2 1242.22  5171.8 1245.69  5190.6 1247.06
  5216.3 1247.79  5221.4 1247.33  5241.7 1248.42  5265.8 1248.57  5292.9 1249.63
  5310.2 1248.98  5425.8 1251.19  5446.2 1250.49  5458.8 1251.30  5528.0 1251.99
#Mann=3,-1,0
  4406.4    0.05       0  4984.1    0.03       0  4988.1    0.05       0
Bank Sta=4984.1,4988.1
Exp/Cntr=0.3,0.1

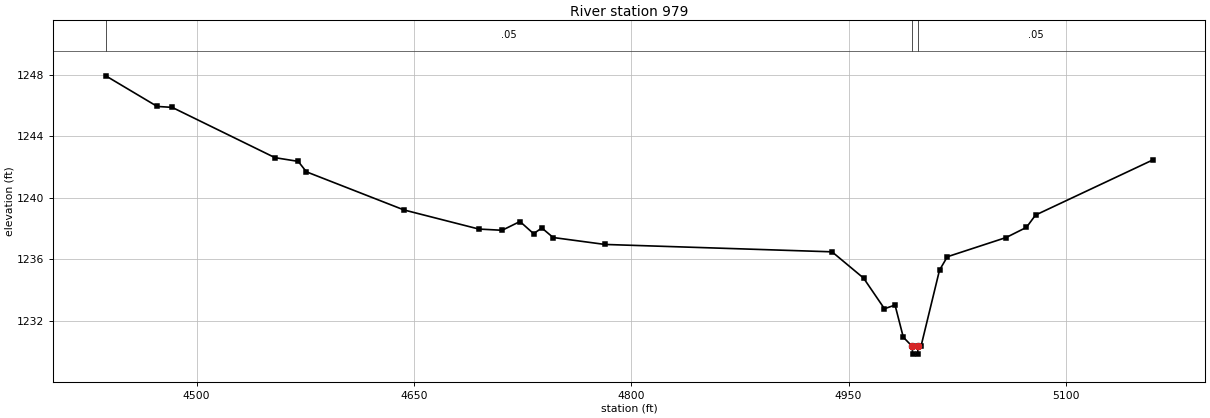
Type RM Length L Ch R = 1,979,0,0,0
BEGIN DESCRIPTION:
LITTLE LLANO 023 1.0
END DESCRIPTION:
XS GIS Cut Line= 3
      2832555.66     10213353.10      2833047.75     10213626.00
      2833205.64     10213653.10
#Sta/Elev= 30
  4437.3 1247.93  4472.8 1245.94  4483.1 1245.88  4554.1 1242.61  4570.1 1242.37
  4575.8 1241.69  4643.2 1239.21  4694.8 1237.97  4710.9 1237.89  4723.2 1238.46
  4732.6 1237.67  4738.3 1238.04  4746.1 1237.42  4781.8 1236.97  4938.6 1236.49
  4960.4 1234.78  4974.8 1232.79  4982.1 1233.03  4987.8 1230.94  4994.0 1230.34
  4994.2 1229.84  4997.7 1229.84  4998.0 1230.34  5000.0 1230.34  5012.8 1235.30
  5018.2 1236.17  5058.8 1237.42  5072.8 1238.08  5079.1 1238.88  5160.2 1242.47
#Mann=3,-1,0
  4437.3    0.05       0  4994.0    0.05       0  4998.0    0.05       0
Bank Sta=4994,4998
Exp/Cntr=0.3,0.1

Chan Stop Cuts=-1