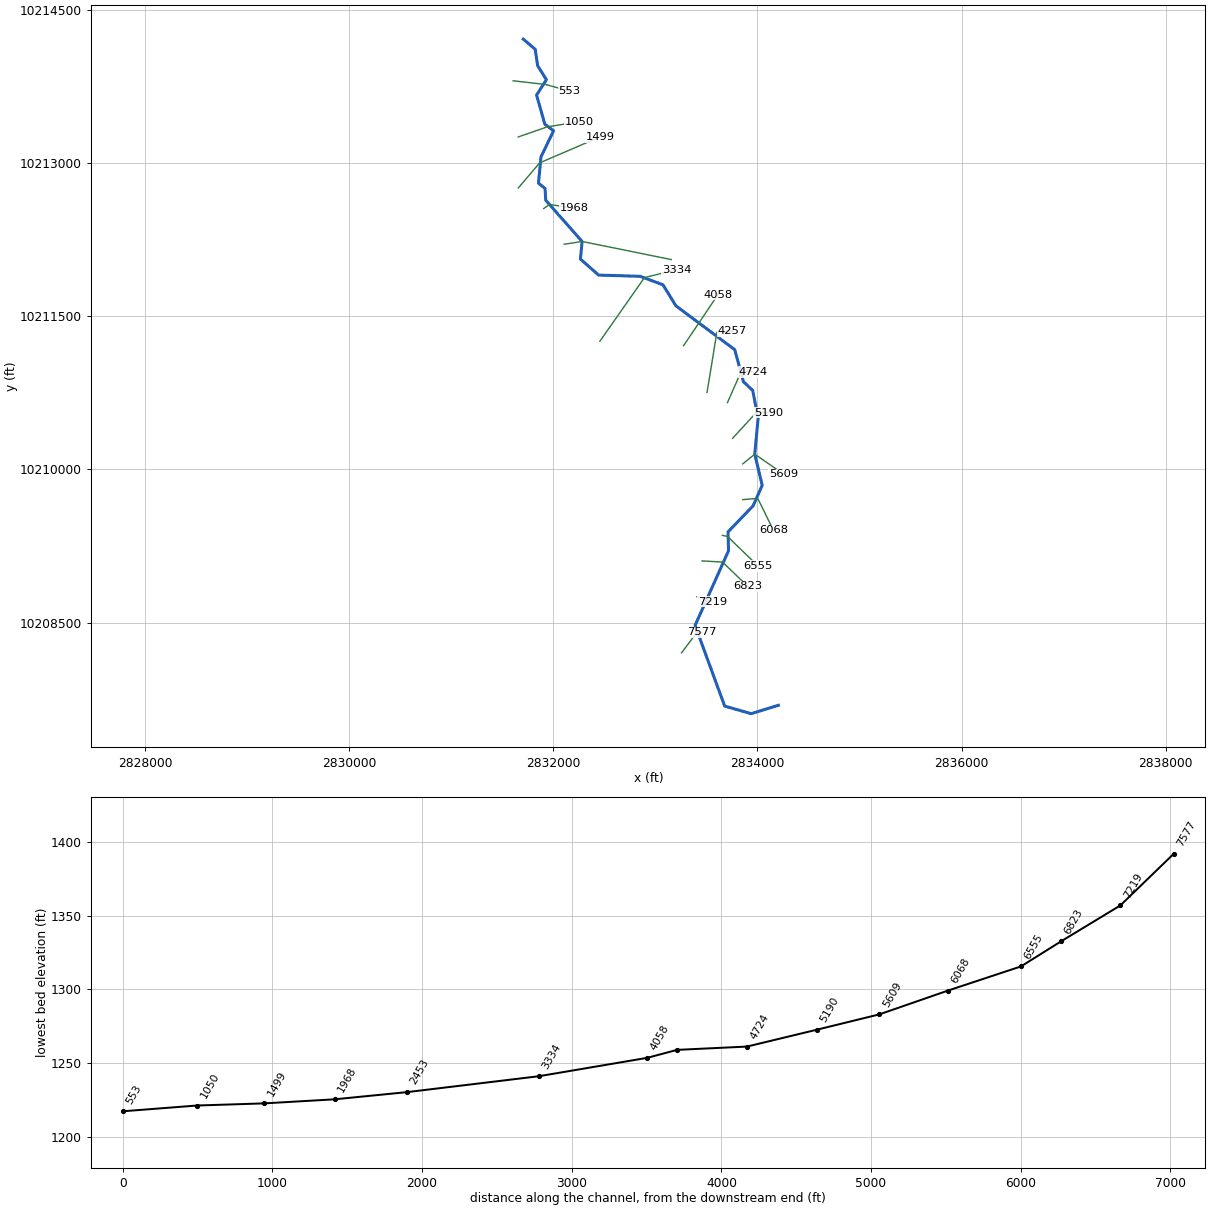
--- LITTLE LLANO 024.prj (project) ---

Proj Title=LITTLE LLANO 024 Base Level Engineering
Current Plan=p01
Default Exp/Contr=0.3,0.1
English Units
Geom File=g01
Flow File=f01
Plan File=p01
BEGIN DESCRIPTION:
LITTLE LLANO 024
END DESCRIPTION:

--- LITTLE LLANO 024.p01 (plan) ---

Plan Title=Multiple Run
Short Identifier=Multiple
Geom File=g01
Flow File=f01
Subcritical Flow
K Sum by GR= 0
Std Step Tol= 0.01
Critical Tol= 0.01
Num of Std Step Trials= 20
Max Error Tol= 0.3
Flow Tol Ratio= 0.001
Split Flow NTrial= 30
Split Flow Tol= 0.02
Split Flow Ratio= 0.02
Log Output Level= 0
Friction Slope Method= 1
Unsteady Friction Slope Method= 2
Unsteady Bridges Friction Slope Method= 1
Parabolic Critical Depth
Global Vel Dist=  1 , 1 , 1
Global Log Level= 0
CheckData=True
Encroach Param= -1, 0, 0, 0
BEGIN DESCRIPTION:
Multiple Run
END DESCRIPTION:

--- LITTLE LLANO 024.f01 (steady flow) ---

Flow Title=Multiple
Number of Profiles=7
Profile Names=10-year,25-year,50-year,1pct_min,100-year,1pct_plu,500-year
River Rch & RM= LITTLE LLANO 024,Reach-1,7577
      46      70     100      49     147     445     355
River Rch & RM= LITTLE LLANO 024,Reach-1,2453
      60     105     160      81     245     740     627
Boundary for River Rch & Prof#=LITTLE LLANO 024,Reach-1,1
Up Type=0
Dn Type=3
Dn Slope=0.005
Boundary for River Rch & Prof#=LITTLE LLANO 024,Reach-1,2
Up Type=0
Dn Type=3
Dn Slope=0.005
Boundary for River Rch & Prof#=LITTLE LLANO 024,Reach-1,3
Up Type=0
Dn Type=3
Dn Slope=0.005
Boundary for River Rch & Prof#=LITTLE LLANO 024,Reach-1,4
Up Type=0
Dn Type=3
Dn Slope=0.005
Boundary for River Rch & Prof#=LITTLE LLANO 024,Reach-1,5
Up Type=0
Dn Type=3
Dn Slope=0.005
Boundary for River Rch & Prof#=LITTLE LLANO 024,Reach-1,6
Up Type=0
Dn Type=3
Dn Slope=0.005
Boundary for River Rch & Prof#=LITTLE LLANO 024,Reach-1,7
Up Type=0
Dn Type=3
Dn Slope=0.005

--- LITTLE LLANO 024.g01 (geometry) ---

Geom Title=Existing Conditions

River Reach=LITTLE LLANO 024,Reach-1
Reach XY= 30
      2834204.50     10207690.00      2833937.75     10207608.00
      2833678.50     10207682.00      2833388.50     10208472.00
      2833716.25     10209203.00      2833711.25     10209387.00
      2833957.25     10209643.00      2834046.25     10209843.00
      2833973.25     10210148.00      2834005.75     10210498.00
      2833953.50     10210771.00      2833862.00     10210858.00
      2833777.00     10211171.00      2833200.00     10211601.00
      2833074.00     10211806.00      2832851.25     10211889.00
      2832443.50     10211901.00      2832265.00     10212058.00
      2832281.75     10212230.00      2831925.25     10212634.00
      2831918.50     10212749.00      2831854.25     10212801.00
      2831878.50     10213057.00      2832002.00     10213314.00
      2831916.50     10213378.00      2831835.50     10213663.00
      2831931.75     10213814.00      2831846.00     10213950.00
      2831822.25     10214111.00      2831705.00     10214211.00

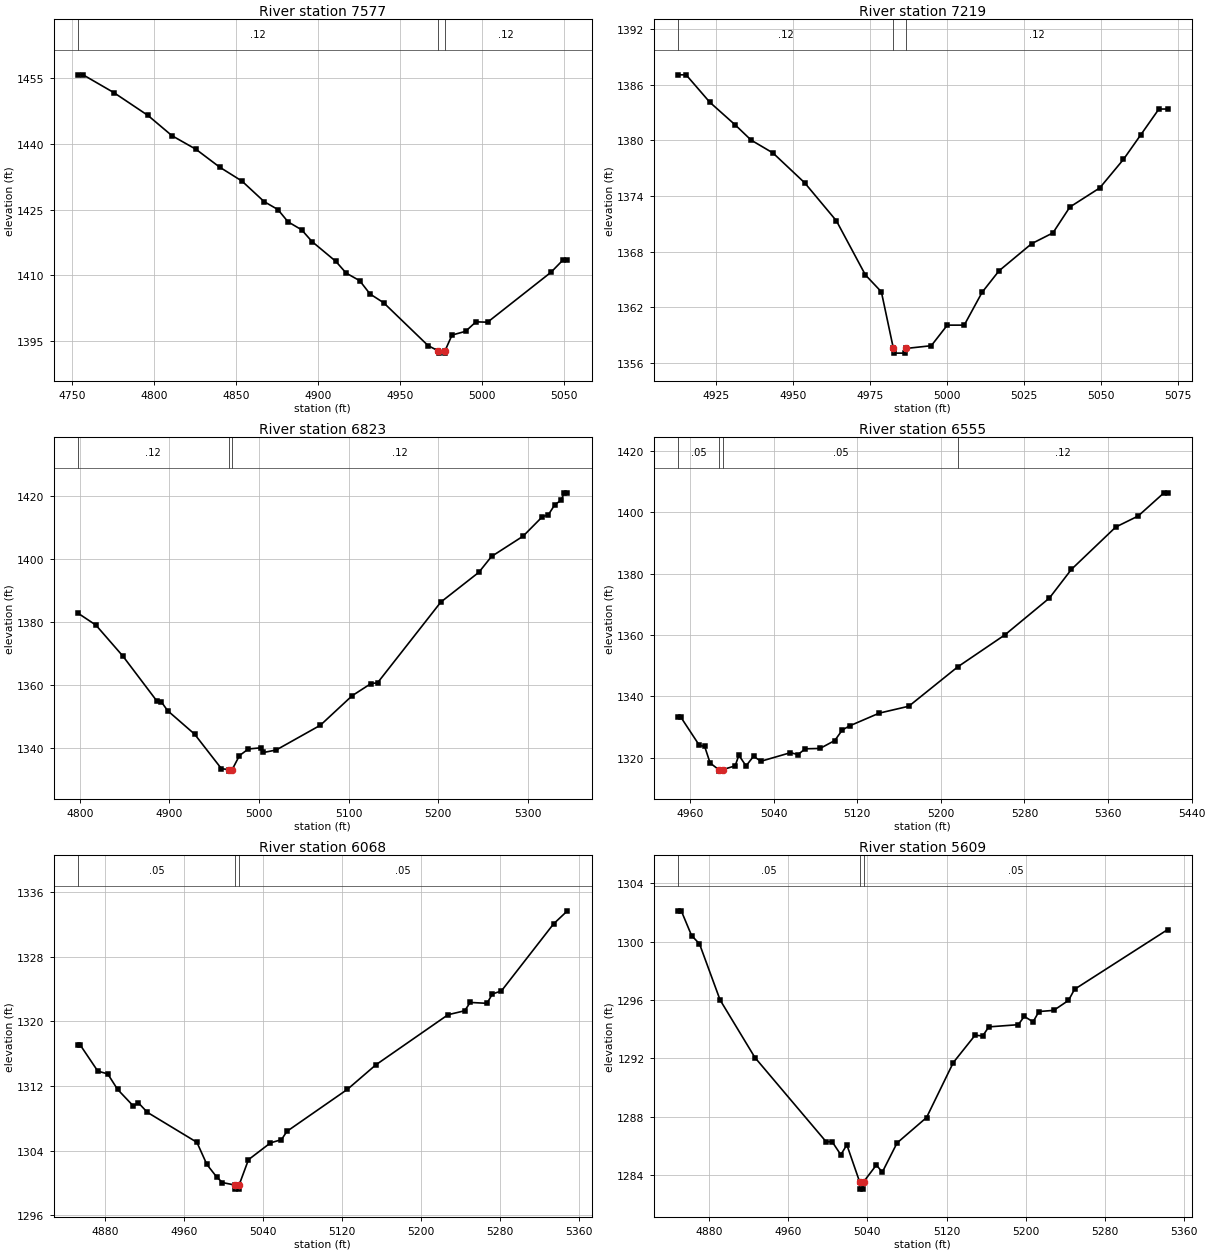
Type RM Length L Ch R = 1,7577,358,358,358
BEGIN DESCRIPTION:
LITTLE LLANO 024 16.0
END DESCRIPTION:
XS GIS Cut Line= 3
      2833255.68     10208203.11      2833403.50     10208400.00
      2833455.71     10208403.11
#Sta/Elev= 30
  4753.8 1455.79  4756.9 1455.79  4775.7 1451.72  4796.5 1446.51  4811.1 1441.90
  4825.7 1438.81  4840.2 1434.72  4853.8 1431.54  4867.3 1426.86  4875.7 1425.05
  4881.9 1422.24  4890.2 1420.42  4896.5 1417.75  4911.1 1413.20  4917.3 1410.56
  4925.6 1408.81  4931.9 1405.78  4940.2 1403.78  4967.3 1394.00  4973.6 1392.78
  4973.9 1392.28  4977.4 1392.28  4977.6 1392.78  4981.9 1396.40  4990.2 1397.26
  4996.5 1399.42  5003.6 1399.34  5042.3 1410.74  5049.8 1413.62  5052.3 1413.62
#Mann=3,-1,0
  4753.8    0.12       0  4973.6    0.07       0  4977.6    0.12       0
Bank Sta=4973.6,4977.6
Exp/Cntr=0.3,0.1

Type RM Length L Ch R = 1,7219,396,396,396
BEGIN DESCRIPTION:
LITTLE LLANO 024 15.0
END DESCRIPTION:
XS GIS Cut Line= 3
      2833405.69     10208753.11      2833490.75     10208733.00
      2833555.70     10208703.10
#Sta/Elev= 27
  4912.6 1387.08  4915.2 1387.08  4922.9 1384.12  4931.2 1381.66  4936.3 1380.04
  4943.4 1378.65  4953.7 1375.43  4964.0 1371.33  4973.4 1365.50  4978.6 1363.67
  4982.5 1357.56  4982.8 1357.06  4986.3 1357.06  4986.5 1357.56  4994.8 1357.86
  5000.0 1360.08  5005.5 1360.08  5011.3 1363.62  5016.8 1365.94  5027.4 1368.87
  5034.3 1370.03  5039.8 1372.82  5049.5 1374.88  5057.2 1377.96  5062.8 1380.60
  5068.7 1383.39  5071.5 1383.39
#Mann=3,-1,0
  4912.6    0.12       0  4982.5    0.07       0  4986.5    0.12       0
Bank Sta=4982.5,4986.5
Exp/Cntr=0.3,0.1

Type RM Length L Ch R = 1,6823,268,268,268
BEGIN DESCRIPTION:
LITTLE LLANO 024 14.0
END DESCRIPTION:
XS GIS Cut Line= 3
      2833455.71     10209103.11      2833657.50     10209092.00
      2833905.70     10208853.09
#Sta/Elev= 30
  4797.9 1382.86  4817.9 1379.07  4848.0 1369.23  4885.9 1354.97  4890.9 1354.71
  4898.0 1351.88  4928.1 1344.42  4958.1 1333.44  4966.1 1333.17  4966.4 1332.67
  4970.1 1333.17  4978.2 1337.61  4988.2 1339.71  5002.2 1340.08  5005.0 1338.59
  5019.2 1339.38  5068.6 1347.26  5104.1 1356.64  5125.2 1360.51  5132.4 1360.72
  5203.1 1386.39  5245.6 1395.86  5259.7 1400.88  5295.0 1407.34  5316.3 1413.46
  5323.3 1414.19  5330.5 1417.37  5337.4 1418.73  5341.0 1421.11  5344.5 1421.11
#Mann=3,-1,0
  4797.9    0.12       0  4966.1    0.07       0  4970.1    0.12       0
Bank Sta=4966.1,4970.1
Exp/Cntr=0.3,0.1

Type RM Length L Ch R = 1,6555,487,487,487
BEGIN DESCRIPTION:
LITTLE LLANO 024 13.0
END DESCRIPTION:
XS GIS Cut Line= 3
      2833655.71     10209353.11      2833706.00     10209343.00
      2834005.65     10209053.15
#Sta/Elev= 30
  4948.7 1333.27  4951.2 1333.27  4969.0 1324.04  4974.1 1323.69  4979.3 1318.29
  4987.5 1316.13  4987.7 1315.63  4991.5 1316.13  5003.3 1317.35  5006.8 1320.81
  5013.7 1317.32  5020.9 1320.47  5027.9 1318.84  5056.2 1321.64  5063.4 1321.02
  5070.3 1322.90  5084.5 1323.02  5098.6 1325.60  5105.8 1329.04  5112.8 1330.37
  5141.1 1334.52  5169.4 1336.77  5216.3 1349.61  5261.4 1360.03  5303.9 1372.00
  5325.0 1381.36  5367.4 1395.14  5388.8 1398.72  5413.5 1406.28  5416.9 1406.28
#Mann=4,-1,0
  4948.7    0.05       0  4987.5    0.05       0  4991.5    0.05       0
  5216.3    0.12       0
Bank Sta=4987.5,4991.5
Exp/Cntr=0.3,0.1

Type RM Length L Ch R = 1,6068,459,459,459
BEGIN DESCRIPTION:
LITTLE LLANO 024 12.0
END DESCRIPTION:
XS GIS Cut Line= 3
      2833855.72     10209703.11      2834002.25     10209716.00
      2834155.69     10209403.10
#Sta/Elev= 30
  4852.9 1317.03  4855.4 1317.03  4872.9 1313.85  4883.0 1313.50  4893.0 1311.58
  4909.0 1309.52  4914.0 1309.93  4923.1 1308.75  4973.3 1305.04  4983.4 1302.30
  4993.4 1300.74  4999.2 1300.06  5012.0 1299.75  5012.2 1299.25  5015.7 1299.25
  5016.0 1299.75  5025.5 1302.89  5047.8 1304.97  5058.9 1305.37  5064.5 1306.40
  5125.7 1311.59  5154.5 1314.62  5227.6 1320.82  5244.5 1321.31  5250.0 1322.34
  5267.0 1322.23  5272.5 1323.38  5281.7 1323.77  5334.5 1332.06  5348.5 1333.67
#Mann=3,-1,0
  4852.9    0.05       0  5012.0    0.05       0  5016.0    0.05       0
Bank Sta=5012,5016
Exp/Cntr=0.3,0.1

Type RM Length L Ch R = 1,5609,419,419,419
BEGIN DESCRIPTION:
LITTLE LLANO 024 11.0
END DESCRIPTION:
XS GIS Cut Line= 3
      2833855.67     10210053.10      2833973.25     10210148.00
      2834255.64     10209953.14
#Sta/Elev= 30
  4848.9 1302.10  4852.1 1302.10  4862.5 1300.41  4870.5 1299.84  4891.3 1296.00
  4926.5 1292.06  4998.4 1286.30  5004.5 1286.30  5013.2 1285.41  5019.3 1286.09
  5032.2 1283.56  5032.4 1283.06  5035.9 1283.06  5036.2 1283.56  5049.1 1284.71
  5055.1 1284.22  5070.0 1286.22  5099.8 1287.96  5126.8 1291.72  5148.8 1293.59
  5156.5 1293.54  5162.6 1294.16  5192.4 1294.31  5198.5 1294.88  5207.3 1294.50
  5213.3 1295.21  5228.2 1295.29  5243.1 1295.97  5249.2 1296.73  5343.1 1300.81
#Mann=3,-1,0
  4848.9    0.05       0  5032.2    0.05       0  5036.2    0.05       0
Bank Sta=5032.2,5036.2
Exp/Cntr=0.3,0.1

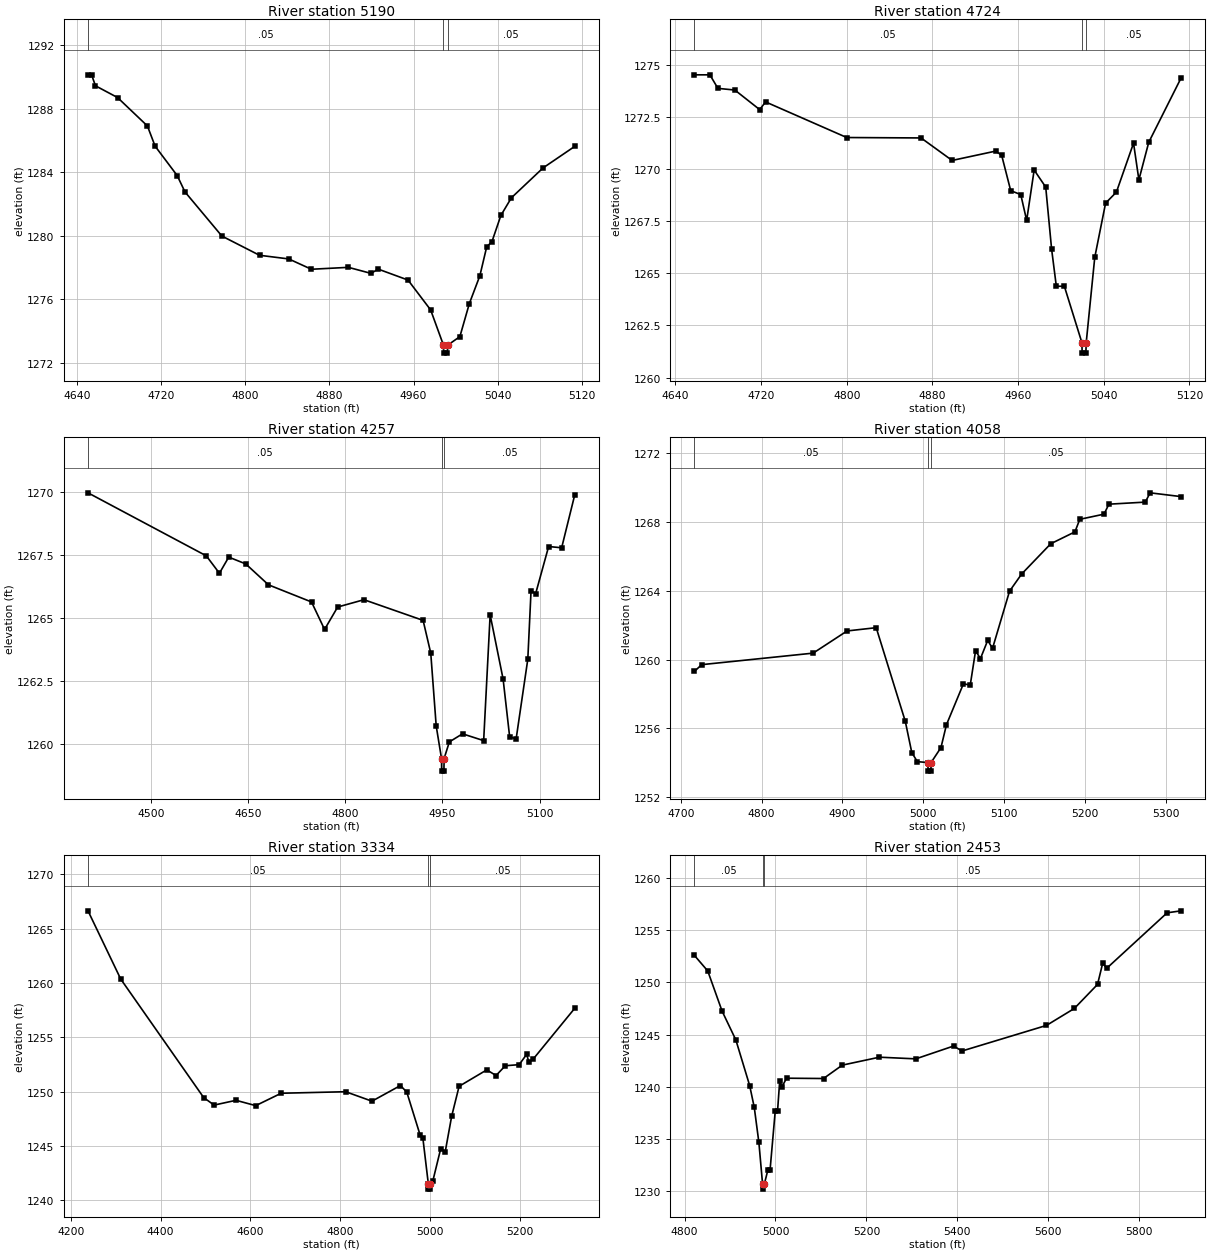
Type RM Length L Ch R = 1,5190,466,466,466
BEGIN DESCRIPTION:
LITTLE LLANO 024 10.0
END DESCRIPTION:
XS GIS Cut Line= 3
      2833755.66     10210303.08      2833992.75     10210560.00
      2834105.64     10210553.11
#Sta/Elev= 30
  4650.4 1290.12  4653.8 1290.12  4657.5 1289.43  4678.5 1288.69  4706.9 1286.90
  4714.2 1285.63  4735.2 1283.78  4742.6 1282.75  4777.7 1279.97  4813.5 1278.76
  4841.3 1278.53  4862.8 1277.88  4898.0 1278.00  4919.5 1277.62  4926.3 1277.89
  4954.7 1277.20  4976.2 1275.32  4988.4 1273.10  4988.6 1272.60  4992.1 1272.60
  4992.4 1273.10  5004.0 1273.64  5013.0 1275.72  5023.0 1277.47  5029.5 1279.29
  5034.5 1279.62  5043.0 1281.27  5053.0 1282.38  5083.1 1284.26  5113.1 1285.61
#Mann=3,-1,0
  4650.4    0.05       0  4988.4    0.03       0  4992.4    0.05       0
Bank Sta=4988.4,4992.4
Exp/Cntr=0.3,0.1

Type RM Length L Ch R = 1,4724,467,467,467
BEGIN DESCRIPTION:
LITTLE LLANO 024 9.0
END DESCRIPTION:
XS GIS Cut Line= 3
      2833705.68     10210653.11      2833844.25     10210966.00
      2833955.71     10210953.11
#Sta/Elev= 30
  4657.8 1274.53  4672.2 1274.53  4679.7 1273.88  4695.5 1273.80  4718.7 1272.86
  4724.2 1273.23  4800.0 1271.52  4869.4 1271.50  4898.4 1270.42  4939.2 1270.87
  4944.7 1270.66  4953.1 1268.97  4962.5 1268.78  4968.0 1267.54  4975.0 1269.96
  4985.8 1269.14  4991.3 1266.16  4995.7 1264.38  5003.2 1264.38  5019.6 1261.67
  5019.8 1261.17  5023.3 1261.17  5023.6 1261.67  5031.6 1265.77  5041.7 1268.37
  5051.8 1268.90  5067.8 1271.25  5072.8 1269.49  5082.0 1271.29  5112.2 1274.38
#Mann=3,-1,0
  4657.8    0.05       0  5019.6    0.05       0  5023.6    0.05       0
Bank Sta=5019.6,5023.6
Exp/Cntr=0.3,0.1

Type RM Length L Ch R = 1,4257,199,199,199
BEGIN DESCRIPTION:
LITTLE LLANO 024 8.0
END DESCRIPTION:
XS GIS Cut Line= 3
      2833505.68     10210753.07      2833602.25     10211342.00
      2833755.65     10211353.11
#Sta/Elev= 30
  4403.2 1269.97  4585.7 1267.47  4605.9 1266.78  4620.3 1267.42  4646.5 1267.15
  4681.6 1266.32  4748.0 1265.64  4768.1 1264.55  4788.3 1265.44  4828.9 1265.73
  4920.1 1264.91  4931.9 1263.61  4940.3 1260.72  4948.5 1259.43  4948.7 1258.93
  4952.2 1258.93  4952.5 1259.43  4960.6 1260.09  4980.9 1260.41  5013.5 1260.14
  5023.5 1265.13  5043.5 1262.58  5053.6 1260.29  5063.6 1260.21  5081.6 1263.37
  5086.6 1266.09  5093.7 1265.97  5113.7 1267.84  5133.8 1267.79  5153.8 1269.87
#Mann=3,-1,0
  4403.2    0.05       0  4948.5    0.03       0  4952.5    0.05       0
Bank Sta=4948.5,4952.5
Exp/Cntr=0.3,0.1

Type RM Length L Ch R = 1,4058,724,724,724
BEGIN DESCRIPTION:
Mapping XS 55b7e3b3
END DESCRIPTION:
XS GIS Cut Line= 2
      2833276.07     10211210.23      2833612.44     10211709.37
#Sta/Elev= 30
  4717.0 1259.32  4725.9 1259.71  4863.8 1260.38  4905.8 1261.67  4941.8 1261.86
  4977.8 1256.41  4985.8 1254.60  4992.7 1254.07  5005.7 1254.02  5006.0 1253.52
  5009.5 1253.52  5009.7 1254.02  5021.9 1254.89  5028.7 1256.22  5049.7 1258.60
  5058.1 1258.52  5064.7 1260.52  5070.7 1260.06  5079.7 1261.12  5085.7 1260.66
  5106.7 1263.98  5121.7 1264.98  5157.7 1266.74  5187.6 1267.43  5193.6 1268.16
  5223.6 1268.46  5229.6 1269.04  5274.6 1269.16  5280.6 1269.70  5318.9 1269.48
#Mann=3,-1,0
  4717.0    0.05       0  5005.7    0.03       0  5009.7    0.05       0
Bank Sta=5005.7,5009.7
Exp/Cntr=0.3,0.1

Type RM Length L Ch R = 1,3334,881,881,881
BEGIN DESCRIPTION:
LITTLE LLANO 024 6.0
END DESCRIPTION:
XS GIS Cut Line= 3
      2832455.66     10211253.07      2832892.75     10211877.00
      2833205.73     10211953.12
#Sta/Elev= 30
  4238.2 1266.63  4311.0 1260.36  4495.9 1249.45  4519.1 1248.76  4567.9 1249.20
  4611.8 1248.71  4668.5 1249.85  4812.1 1249.99  4870.7 1249.12  4934.2 1250.56
  4948.3 1249.95  4978.0 1246.00  4984.1 1245.72  4996.2 1241.53  4996.4 1241.03
  4999.9 1241.03  5000.2 1241.53  5006.4 1241.80  5023.6 1244.71  5033.9 1244.47
  5048.2 1247.73  5064.8 1250.49  5126.5 1252.00  5147.1 1251.48  5167.7 1252.38
  5198.6 1252.48  5215.1 1253.42  5220.3 1252.73  5229.4 1252.97  5322.1 1257.65
#Mann=3,-1,0
  4238.2    0.05       0  4996.2    0.05       0  5000.2    0.05       0
Bank Sta=4996.2,5000.2
Exp/Cntr=0.3,0.1

Type RM Length L Ch R = 1,2453,485,485,485
BEGIN DESCRIPTION:
LITTLE LLANO 024 5.0
END DESCRIPTION:
XS GIS Cut Line= 3
      2832105.69     10212203.11      2832281.75     10212230.00
      2833155.73     10212053.10
#Sta/Elev= 30
  4821.9 1252.57  4851.1 1251.09  4882.6 1247.25  4912.9 1244.49  4943.3 1240.12
  4953.4 1238.03  4963.5 1234.69  4971.6 1230.72  4971.9 1230.22  4975.6 1230.72
  4983.1 1232.02  4988.1 1232.05  4999.5 1237.71  5004.6 1237.71  5009.3 1240.57
  5014.4 1240.02  5024.4 1240.83  5105.6 1240.80  5146.9 1242.08  5228.5 1242.84
  5308.5 1242.68  5391.7 1243.91  5409.9 1243.43  5595.8 1245.88  5657.0 1247.50
  5708.0 1249.80  5719.3 1251.82  5728.4 1251.35  5861.0 1256.65  5891.7 1256.84
#Mann=3,-1,0
  4821.9    0.05       0  4971.6    0.05       0  4975.6    0.05       0
Bank Sta=4971.6,4975.6
Exp/Cntr=0.3,0.1

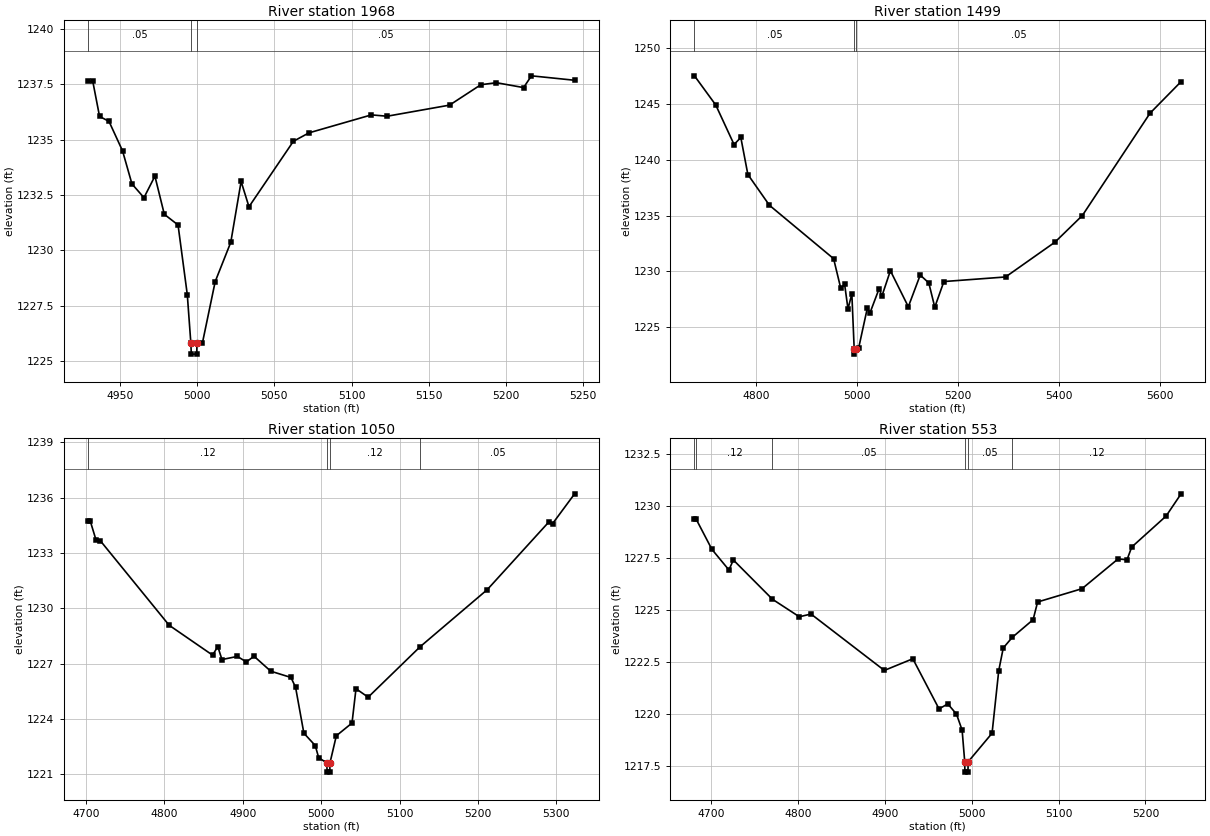
Type RM Length L Ch R = 1,1968,469,469,469
BEGIN DESCRIPTION:
LITTLE LLANO 024 4.0
END DESCRIPTION:
XS GIS Cut Line= 3
      2831905.65     10212553.09      2831964.25     10212593.00
      2832205.68     10212553.11
#Sta/Elev= 30
  4929.1 1237.62  4932.2 1237.62  4936.6 1236.04  4942.7 1235.82  4951.5 1234.49
  4957.6 1233.00  4965.4 1232.38  4972.5 1233.35  4978.6 1231.63  4987.5 1231.15
  4993.5 1228.01  4995.8 1225.83  4996.1 1225.33  4999.6 1225.33  4999.8 1225.83
  5003.3 1225.83  5011.6 1228.60  5021.7 1230.37  5028.4 1233.11  5033.5 1231.97
  5062.3 1234.92  5072.4 1235.30  5112.9 1236.11  5123.1 1236.05  5163.6 1236.55
  5183.9 1237.47  5194.0 1237.56  5211.6 1237.34  5216.7 1237.87  5244.7 1237.67
#Mann=3,-1,0
  4929.1    0.05       0  4995.8    0.05       0  4999.8    0.05       0
Bank Sta=4995.8,4999.8
Exp/Cntr=0.3,0.1

Type RM Length L Ch R = 1,1499,449,449,449
BEGIN DESCRIPTION:
LITTLE LLANO 024 3.0
END DESCRIPTION:
XS GIS Cut Line= 3
      2831655.67     10212753.09      2831865.25     10212999.00
      2832455.69     10213253.11
#Sta/Elev= 30
  4676.9 1247.53  4719.2 1244.91  4755.5 1241.37  4768.9 1242.00  4782.9 1238.68
  4825.7 1235.92  4953.1 1231.13  4967.3 1228.47  4975.0 1228.82  4981.6 1226.63
  4989.3 1227.97  4993.9 1223.07  4994.1 1222.57  4997.9 1223.07  5003.0 1223.16
  5019.9 1226.67  5025.4 1226.28  5043.5 1228.45  5048.9 1227.77  5065.8 1230.05
  5101.4 1226.82  5125.0 1229.66  5142.0 1228.96  5153.9 1226.78  5172.0 1229.08
  5294.4 1229.49  5392.4 1232.61  5446.8 1235.00  5581.2 1244.18  5642.8 1247.01
#Mann=3,-1,0
  4676.9    0.05       0  4993.9    0.05       0  4997.9    0.05       0
Bank Sta=4993.9,4997.9
Exp/Cntr=0.3,0.1

Type RM Length L Ch R = 1,1050,497,497,497
BEGIN DESCRIPTION:
LITTLE LLANO 024 2.0
END DESCRIPTION:
XS GIS Cut Line= 3
      2831655.67     10213253.11      2831936.50     10213351.00
      2832255.67     10213403.11
#Sta/Elev= 30
  4702.6 1234.75  4705.3 1234.75  4712.9 1233.69  4718.1 1233.67  4806.1 1229.08
  4861.5 1227.46  4868.2 1227.92  4873.5 1227.22  4893.2 1227.39  4904.6 1227.09
  4914.4 1227.40  4935.7 1226.59  4961.5 1226.25  4967.4 1225.72  4978.0 1223.23
  4992.5 1222.56  4996.9 1221.90  5007.3 1221.62  5007.6 1221.12  5011.1 1221.12
  5011.3 1221.62  5019.4 1223.09  5039.4 1223.78  5044.5 1225.64  5060.0 1225.18
  5126.2 1227.91  5212.0 1231.01  5290.2 1234.66  5295.2 1234.58  5323.4 1236.20
#Mann=4,-1,0
  4702.6    0.12       0  5007.3    0.07       0  5011.3    0.12       0
  5126.2    0.05       0
Bank Sta=5007.3,5011.3
Exp/Cntr=0.3,0.1

Type RM Length L Ch R = 1,553,0,0,0
BEGIN DESCRIPTION:
LITTLE LLANO 024 1.0
END DESCRIPTION:
XS GIS Cut Line= 3
      2831605.70     10213803.11      2831923.25     10213767.00
      2832155.73     10213703.10
#Sta/Elev= 30
  4680.4 1229.35  4682.5 1229.35  4700.5 1227.91  4720.1 1226.92  4725.2 1227.40
  4770.3 1225.51  4801.2 1224.67  4814.7 1224.80  4899.2 1222.09  4932.0 1222.65
  4962.2 1220.24  4972.3 1220.48  4982.3 1219.99  4988.8 1219.22  4991.8 1217.70
  4992.0 1217.20  4995.5 1217.20  4995.8 1217.70  5023.3 1219.07  5031.0 1222.08
  5036.2 1223.17  5046.6 1223.68  5070.6 1224.53  5075.8 1225.38  5127.0 1226.02
  5168.5 1227.45  5178.8 1227.41  5184.2 1228.02  5223.8 1229.51  5241.1 1230.58
#Mann=6,-1,0
  4680.4    0.05       0  4682.5    0.12       0  4770.3    0.05       0
  4991.8    0.05       0  4995.8    0.05       0  5046.6    0.12       0
Bank Sta=4991.8,4995.8
Exp/Cntr=0.3,0.1

Chan Stop Cuts=-1