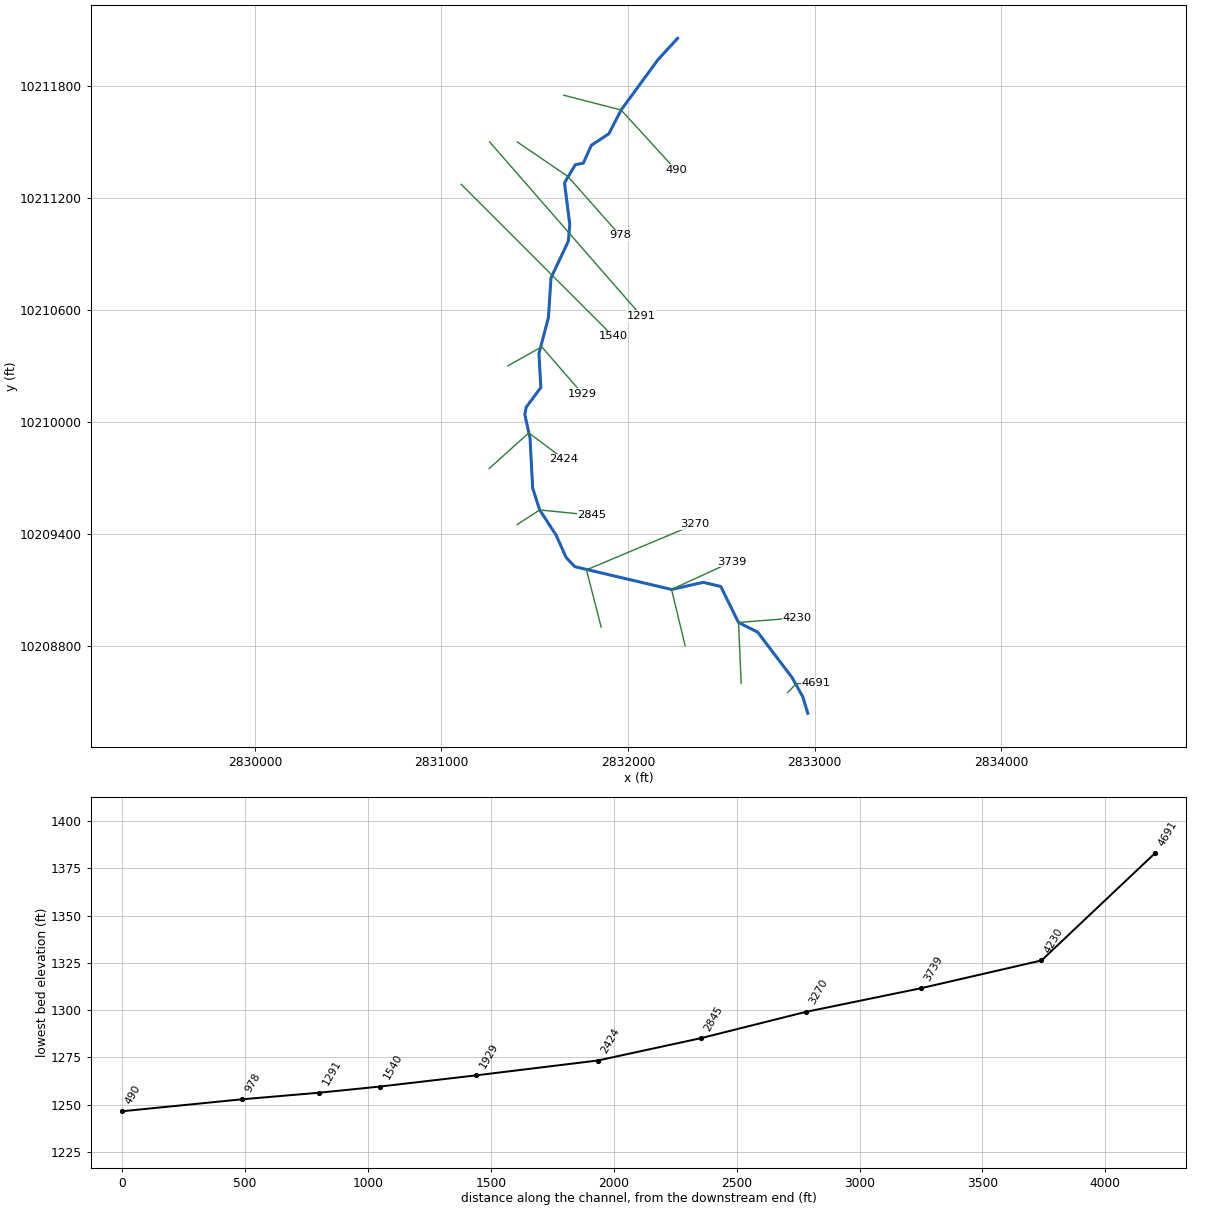
--- LITTLE LLANO 025.prj (project) ---

Proj Title=LITTLE LLANO 025 Base Level Engineering
Current Plan=p01
Default Exp/Contr=0.3,0.1
English Units
Geom File=g01
Flow File=f01
Plan File=p01
BEGIN DESCRIPTION:
LITTLE LLANO 025
END DESCRIPTION:

--- LITTLE LLANO 025.p01 (plan) ---

Plan Title=Multiple Run
Short Identifier=Multiple
Geom File=g01
Flow File=f01
Subcritical Flow
K Sum by GR= 0
Std Step Tol= 0.01
Critical Tol= 0.01
Num of Std Step Trials= 20
Max Error Tol= 0.3
Flow Tol Ratio= 0.001
Split Flow NTrial= 30
Split Flow Tol= 0.02
Split Flow Ratio= 0.02
Log Output Level= 0
Friction Slope Method= 1
Unsteady Friction Slope Method= 2
Unsteady Bridges Friction Slope Method= 1
Parabolic Critical Depth
Global Vel Dist=  1 , 1 , 1
Global Log Level= 0
CheckData=True
Encroach Param= -1, 0, 0, 0
BEGIN DESCRIPTION:
Multiple Run
END DESCRIPTION:

--- LITTLE LLANO 025.f01 (steady flow) ---

Flow Title=Multiple
Number of Profiles=7
Profile Names=10-year,25-year,50-year,1pct_min,100-year,1pct_plu,500-year
River Rch & RM= LITTLE LLANO 025,Reach-1,4691
      30      39      52      24      72     217     158
Boundary for River Rch & Prof#=LITTLE LLANO 025,Reach-1,1
Up Type=0
Dn Type=3
Dn Slope=0.005
Boundary for River Rch & Prof#=LITTLE LLANO 025,Reach-1,2
Up Type=0
Dn Type=3
Dn Slope=0.005
Boundary for River Rch & Prof#=LITTLE LLANO 025,Reach-1,3
Up Type=0
Dn Type=3
Dn Slope=0.005
Boundary for River Rch & Prof#=LITTLE LLANO 025,Reach-1,4
Up Type=0
Dn Type=3
Dn Slope=0.005
Boundary for River Rch & Prof#=LITTLE LLANO 025,Reach-1,5
Up Type=0
Dn Type=3
Dn Slope=0.005
Boundary for River Rch & Prof#=LITTLE LLANO 025,Reach-1,6
Up Type=0
Dn Type=3
Dn Slope=0.005
Boundary for River Rch & Prof#=LITTLE LLANO 025,Reach-1,7
Up Type=0
Dn Type=3
Dn Slope=0.005

--- LITTLE LLANO 025.g01 (geometry) ---

Geom Title=Existing Conditions

River Reach=LITTLE LLANO 025,Reach-1
Reach XY= 30
      2832962.75     10208441.00      2832935.50     10208531.00
      2832878.00     10208634.00      2832694.25     10208876.00
      2832591.50     10208928.00      2832496.50     10209121.00
      2832402.25     10209143.00      2832232.75     10209105.00
      2831714.75     10209227.00      2831668.00     10209276.00
      2831614.25     10209396.00      2831526.25     10209531.00
      2831488.50     10209648.00      2831474.50     10209916.00
      2831446.50     10210042.00      2831454.00     10210082.00
      2831532.50     10210187.00      2831522.25     10210369.00
      2831573.00     10210562.00      2831586.75     10210774.00
      2831680.00     10210972.00      2831687.50     10211060.00
      2831659.25     10211284.00      2831717.25     10211381.00
      2831759.75     10211389.00      2831803.00     10211485.00
      2831897.25     10211547.00      2831962.50     10211674.00
      2832160.25     10211944.00      2832265.00     10212058.00

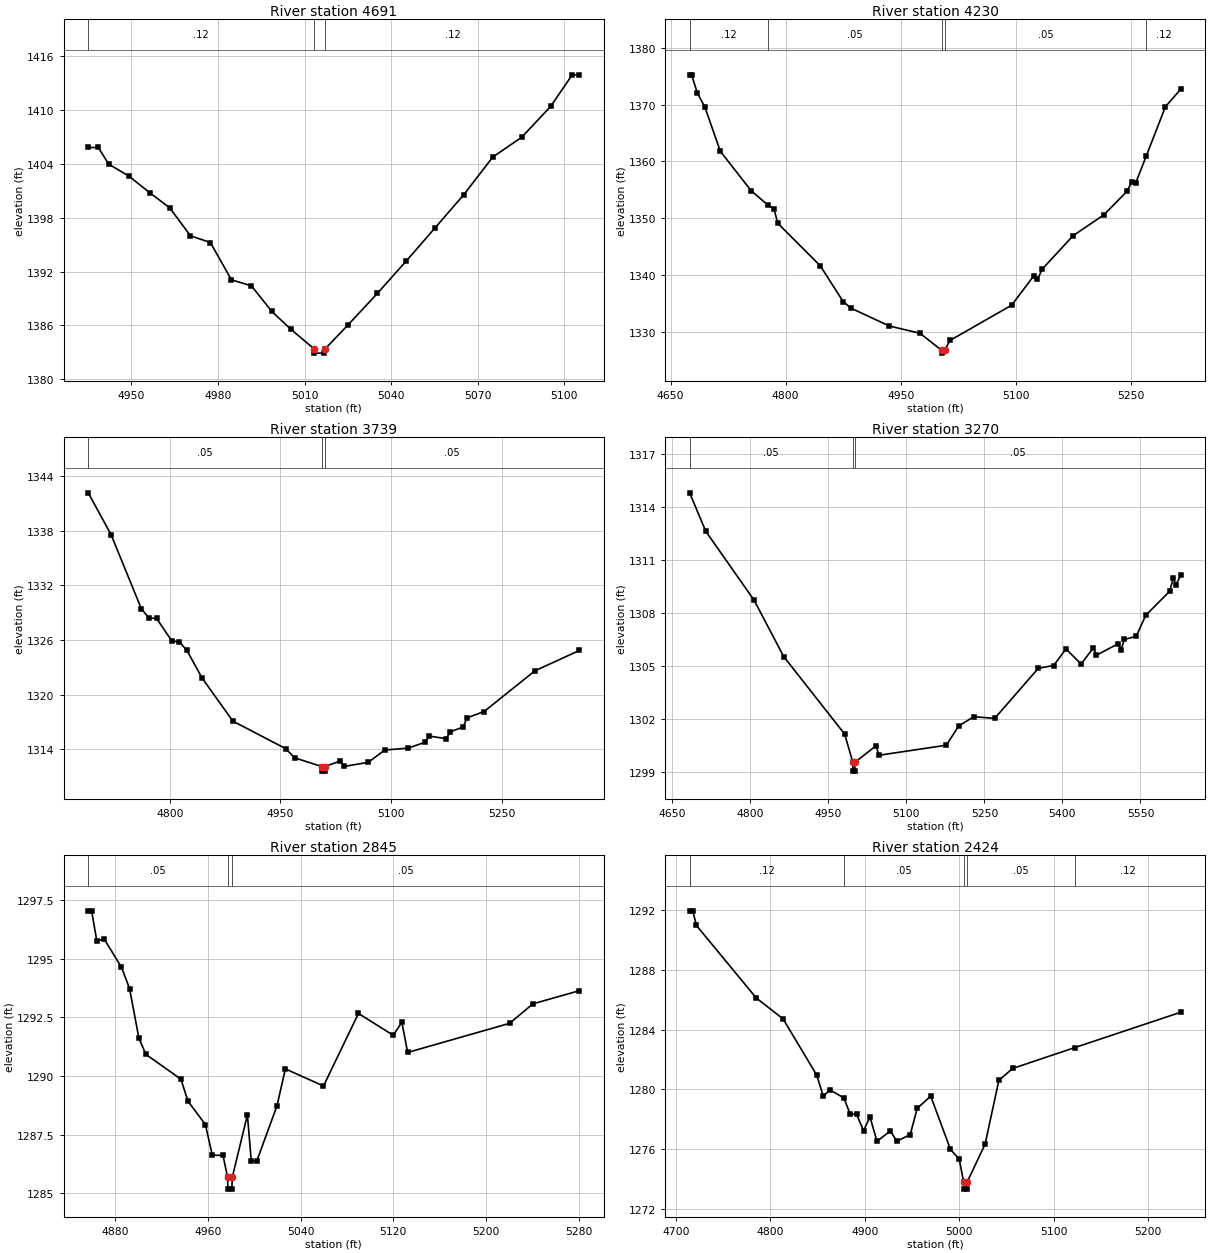
Type RM Length L Ch R = 1,4691,461,461,461
BEGIN DESCRIPTION:
LITTLE LLANO 025 10.0
END DESCRIPTION:
XS GIS Cut Line= 3
      2832855.66     10208553.08      2832900.50     10208600.00
      2833005.65     10208603.11
#Sta/Elev= 26
  4935.1 1405.83  4938.6 1405.83  4942.2 1403.97  4949.1 1402.66  4956.4 1400.79
  4963.3 1399.11  4970.5 1395.99  4977.4 1395.24  4984.7 1391.08  4991.6 1390.41
  4998.7 1387.55  5005.2 1385.59  5013.2 1383.41  5013.4 1382.91  5016.9 1382.91
  5017.2 1383.41  5025.2 1386.10  5035.2 1389.56  5045.2 1393.17  5055.2 1396.87
  5065.2 1400.59  5075.2 1404.77  5085.2 1406.97  5095.2 1410.40  5102.7 1413.93
  5105.2 1413.93
#Mann=3,-1,0
  4935.1    0.12       0  5013.2    0.07       0  5017.2    0.12       0
Bank Sta=5013.2,5017.2
Exp/Cntr=0.3,0.1

Type RM Length L Ch R = 1,4230,491,491,491
BEGIN DESCRIPTION:
LITTLE LLANO 025 9.0
END DESCRIPTION:
XS GIS Cut Line= 3
      2832605.68     10208603.11      2832591.50     10208928.00
      2832905.70     10208953.11
#Sta/Elev= 30
  4674.8 1375.22  4677.3 1375.22  4684.8 1372.06  4694.8 1369.49  4714.8 1361.78
  4754.9 1354.85  4776.9 1352.30  4784.7 1351.66  4789.7 1349.11  4845.0 1341.65
  4875.0 1335.33  4885.0 1334.19  4935.0 1331.05  4975.1 1329.76  5003.3 1326.77
  5003.6 1326.27  5007.3 1326.77  5014.2 1328.50  5094.5 1334.69  5123.2 1339.81
  5128.3 1339.23  5134.6 1341.07  5174.7 1346.92  5214.9 1350.60  5245.0 1354.74
  5251.2 1356.40  5256.2 1356.15  5270.2 1360.97  5295.1 1369.61  5315.2 1372.73
#Mann=5,-1,0
  4674.8    0.12       0  4776.9    0.05       0  5003.3    0.05       0
  5007.3    0.05       0  5270.2    0.12       0
Bank Sta=5003.3,5007.3
Exp/Cntr=0.3,0.1

Type RM Length L Ch R = 1,3739,469,469,469
BEGIN DESCRIPTION:
LITTLE LLANO 025 8.0
END DESCRIPTION:
XS GIS Cut Line= 3
      2832305.69     10208803.09      2832232.75     10209105.00
      2832555.70     10209253.12
#Sta/Elev= 30
  4689.4 1342.19  4720.3 1337.60  4761.4 1329.44  4771.7 1328.41  4782.0 1328.38
  4802.6 1325.90  4812.9 1325.79  4823.2 1324.85  4843.7 1321.82  4885.5 1317.07
  4956.9 1314.05  4969.3 1313.03  5006.1 1312.07  5006.3 1311.57  5009.8 1311.57
  5010.1 1312.07  5031.1 1312.69  5036.6 1312.09  5069.2 1312.54  5091.2 1313.89
  5123.1 1314.10  5146.1 1314.75  5151.6 1315.43  5174.6 1315.14  5180.1 1315.89
  5197.6 1316.43  5203.1 1317.44  5226.1 1318.13  5295.0 1322.61  5355.3 1324.85
#Mann=3,-1,0
  4689.4    0.05       0  5006.1    0.05       0  5010.1    0.05       0
Bank Sta=5006.1,5010.1
Exp/Cntr=0.3,0.1

Type RM Length L Ch R = 1,3270,425,425,425
BEGIN DESCRIPTION:
LITTLE LLANO 025 7.0
END DESCRIPTION:
XS GIS Cut Line= 3
      2831855.68     10208903.13      2831777.00     10209210.00
      2832355.71     10209453.12
#Sta/Elev= 30
  4683.2 1314.82  4714.2 1312.64  4807.1 1308.73  4864.1 1305.53  4981.3 1301.13
  4997.0 1299.53  4997.3 1299.03  5000.8 1299.03  5001.0 1299.53  5041.6 1300.47
  5047.1 1299.93  5176.7 1300.50  5200.5 1301.59  5229.6 1302.12  5269.7 1302.02
  5353.8 1304.87  5383.0 1305.02  5406.8 1305.96  5435.9 1305.11  5459.7 1306.03
  5465.1 1305.60  5507.2 1306.26  5512.6 1305.92  5519.2 1306.50  5541.8 1306.68
  5560.2 1307.87  5606.0 1309.23  5613.1 1309.96  5618.5 1309.61  5627.7 1310.15
#Mann=3,-1,0
  4683.2    0.05       0  4997.0    0.05       0  5001.0    0.05       0
Bank Sta=4997,5001
Exp/Cntr=0.3,0.1

Type RM Length L Ch R = 1,2845,421,421,421
BEGIN DESCRIPTION:
LITTLE LLANO 025 6.0
END DESCRIPTION:
XS GIS Cut Line= 3
      2831405.71     10209453.13      2831526.25     10209531.00
      2831805.66     10209503.11
#Sta/Elev= 30
  4856.5 1297.03  4859.4 1297.03  4864.0 1295.73  4870.0 1295.85  4885.2 1294.63
  4892.2 1293.72  4900.3 1291.60  4906.3 1290.92  4936.6 1289.86  4942.6 1288.93
  4957.7 1287.93  4963.7 1286.62  4972.9 1286.62  4976.9 1285.68  4977.1 1285.18
  4980.6 1285.18  4980.9 1285.68  4994.0 1288.34  4997.3 1286.39  5002.2 1286.39
  5019.5 1288.72  5026.8 1290.30  5059.7 1289.57  5089.9 1292.66  5120.0 1291.73
  5127.4 1292.29  5132.4 1291.00  5220.5 1292.24  5240.6 1293.07  5280.8 1293.63
#Mann=3,-1,0
  4856.5    0.05       0  4976.9    0.05       0  4980.9    0.05       0
Bank Sta=4976.9,4980.9
Exp/Cntr=0.3,0.1

Type RM Length L Ch R = 1,2424,495,495,495
BEGIN DESCRIPTION:
LITTLE LLANO 025 5.0
END DESCRIPTION:
XS GIS Cut Line= 3
      2831255.69     10209753.12      2831468.00     10209944.00
      2831655.70     10209803.10
#Sta/Elev= 30
  4714.5 1291.94  4717.9 1291.94  4721.6 1290.97  4785.1 1286.11  4813.5 1284.71
  4849.0 1280.96  4856.1 1279.54  4862.9 1279.97  4877.8 1279.43  4884.5 1278.35
  4891.3 1278.33  4898.7 1277.24  4905.5 1278.15  4912.9 1276.53  4927.1 1277.22
  4933.9 1276.53  4948.1 1276.98  4955.5 1278.73  4969.8 1279.55  4990.7 1275.99
  5000.0 1275.33  5004.6 1273.83  5004.8 1273.33  5008.3 1273.33  5008.6 1273.83
  5027.4 1276.34  5042.0 1280.61  5056.6 1281.40  5122.6 1282.80  5234.7 1285.16
#Mann=5,-1,0
  4714.5    0.12       0  4877.8    0.05       0  5004.6    0.05       0
  5008.6    0.05       0  5122.6    0.12       0
Bank Sta=5004.6,5008.6
Exp/Cntr=0.3,0.1

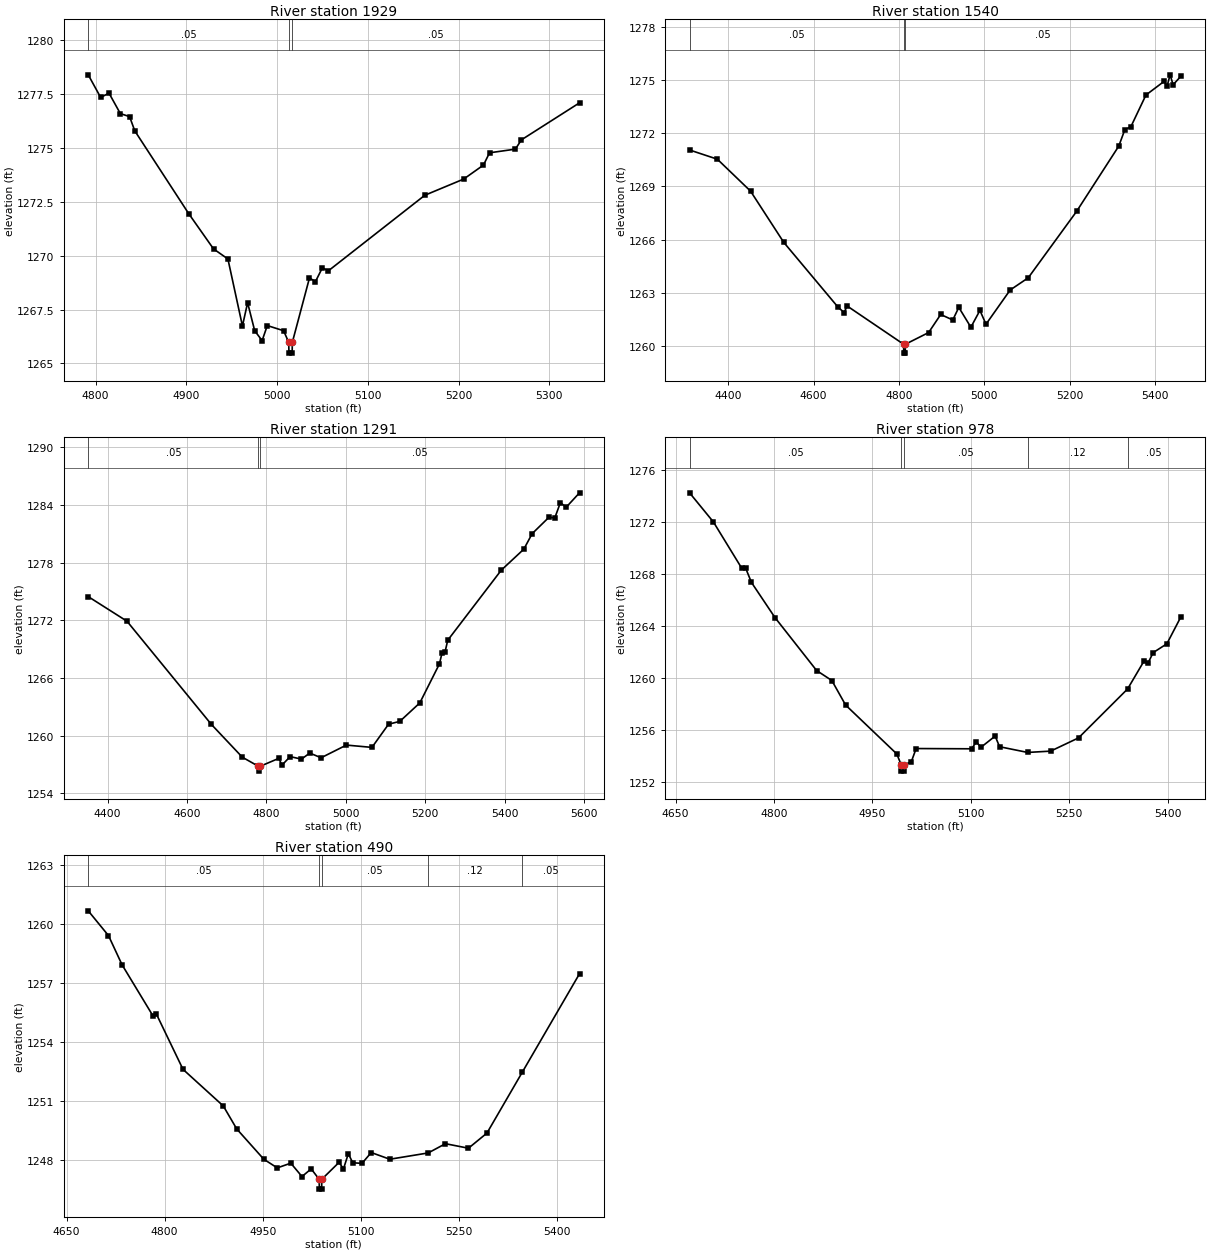
Type RM Length L Ch R = 1,1929,389,389,389
BEGIN DESCRIPTION:
LITTLE LLANO 025 4.0
END DESCRIPTION:
XS GIS Cut Line= 3
      2831355.68     10210303.11      2831537.25     10210405.00
      2831755.68     10210153.12
#Sta/Elev= 30
  4791.8 1278.40  4805.5 1277.35  4814.7 1277.55  4827.2 1276.60  4837.4 1276.46
  4843.1 1275.80  4902.5 1271.96  4929.9 1270.32  4945.8 1269.85  4961.8 1266.74
  4967.5 1267.82  4975.3 1266.52  4983.5 1266.06  4989.2 1266.76  5007.2 1266.52
  5012.8 1265.98  5013.1 1265.48  5016.6 1265.48  5016.8 1265.98  5035.7 1268.97
  5042.3 1268.80  5049.9 1269.44  5056.5 1269.30  5162.9 1272.81  5205.7 1273.56
  5227.5 1274.21  5234.2 1274.78  5262.7 1274.95  5269.3 1275.38  5333.4 1277.10
#Mann=3,-1,0
  4791.8    0.05       0  5012.8    0.05       0  5016.8    0.05       0
Bank Sta=5012.8,5016.8
Exp/Cntr=0.3,0.1

Type RM Length L Ch R = 1,1540,249,249,249
BEGIN DESCRIPTION:
Mapping XS 3ab08502
END DESCRIPTION:
XS GIS Cut Line= 2
      2831105.90     10211275.33      2831919.71     10210461.52
#Sta/Elev= 30
  4309.4 1271.05  4374.5 1270.53  4452.2 1268.73  4530.0 1265.84  4657.3 1262.18
  4671.4 1261.88  4678.5 1262.25  4810.9 1260.09  4811.1 1259.59  4814.6 1259.59
  4814.9 1260.09  4869.4 1260.75  4897.7 1261.77  4926.0 1261.46  4940.1 1262.17
  4968.4 1261.05  4989.6 1262.00  5003.8 1261.22  5060.4 1263.15  5102.8 1263.84
  5215.9 1267.58  5314.9 1271.27  5329.1 1272.20  5343.2 1272.36  5378.5 1274.15
  5421.0 1274.92  5428.0 1274.65  5435.1 1275.29  5442.2 1274.73  5460.3 1275.21
#Mann=3,-1,0
  4309.4    0.05       0  4810.9    0.03       0  4814.9    0.05       0
Bank Sta=4810.9,4814.9
Exp/Cntr=0.3,0.1

Type RM Length L Ch R = 1,1291,313,313,313
BEGIN DESCRIPTION:
Mapping XS d65e3bb1
END DESCRIPTION:
XS GIS Cut Line= 2
      2831257.86     10211503.14      2832071.15     10210570.56
#Sta/Elev= 30
  4351.1 1274.47  4448.7 1271.91  4661.3 1261.17  4739.2 1257.76  4779.9 1256.81
  4780.1 1256.31  4783.9 1256.81  4831.2 1257.64  4838.9 1256.93  4859.7 1257.82
  4888.2 1257.56  4909.1 1258.19  4937.6 1257.70  5001.3 1259.02  5065.7 1258.78
  5107.5 1261.19  5136.0 1261.49  5186.3 1263.41  5235.7 1267.47  5242.3 1268.62
  5249.9 1268.73  5256.6 1269.93  5391.4 1277.22  5448.3 1279.41  5469.2 1281.02
  5511.9 1282.74  5526.2 1282.65  5540.4 1284.26  5554.7 1283.76  5588.5 1285.27
#Mann=3,-1,0
  4351.1    0.05       0  4779.9    0.05       0  4783.9    0.05       0
Bank Sta=4779.9,4783.9
Exp/Cntr=0.3,0.1

Type RM Length L Ch R = 1,978,488,488,488
BEGIN DESCRIPTION:
LITTLE LLANO 025 2.0
END DESCRIPTION:
XS GIS Cut Line= 3
      2831405.65     10211503.14      2831677.25     10211318.00
      2831955.66     10211003.14
#Sta/Elev= 30
  4671.3 1274.27  4707.7 1272.02  4750.6 1268.48  4756.7 1268.48  4765.6 1267.37
  4801.5 1264.66  4865.0 1260.58  4888.2 1259.81  4909.2 1257.92  4987.1 1254.16
  4993.9 1253.33  4994.2 1252.83  4997.7 1252.83  4997.9 1253.33  5009.2 1253.53
  5016.7 1254.57  5101.2 1254.55  5108.7 1255.09  5115.4 1254.66  5137.2 1255.53
  5143.9 1254.71  5186.7 1254.27  5221.7 1254.37  5264.3 1255.39  5339.1 1259.16
  5363.9 1261.29  5370.6 1261.19  5378.1 1261.96  5399.0 1262.64  5420.3 1264.71
#Mann=5,-1,0
  4671.3    0.05       0  4993.9    0.05       0  4997.9    0.05       0
  5186.7    0.12       0  5339.1    0.05       0
Bank Sta=4993.9,4997.9
Exp/Cntr=0.3,0.1

Type RM Length L Ch R = 1,490,0,0,0
BEGIN DESCRIPTION:
LITTLE LLANO 025 1.0
END DESCRIPTION:
XS GIS Cut Line= 3
      2831655.64     10211753.12      2831962.50     10211674.00
      2832255.71     10211353.08
#Sta/Elev= 30
  4683.1 1260.66  4714.1 1259.40  4734.8 1257.92  4782.3 1255.31  4787.4 1255.41
  4828.1 1252.60  4889.7 1250.74  4910.3 1249.57  4951.7 1248.03  4972.3 1247.59
  4993.0 1247.83  5010.1 1247.15  5024.2 1247.54  5036.4 1247.01  5036.7 1246.51
  5040.2 1246.51  5040.4 1247.01  5066.8 1247.87  5073.6 1247.54  5081.0 1248.31
  5087.8 1247.85  5101.9 1247.82  5116.1 1248.37  5144.5 1248.03  5203.2 1248.35
  5229.6 1248.82  5264.8 1248.59  5293.1 1249.36  5347.4 1252.47  5434.7 1257.46
#Mann=5,-1,0
  4683.1    0.05       0  5036.4    0.05       0  5040.4    0.05       0
  5203.2    0.12       0  5347.4    0.05       0
Bank Sta=5036.4,5040.4
Exp/Cntr=0.3,0.1

Chan Stop Cuts=-1