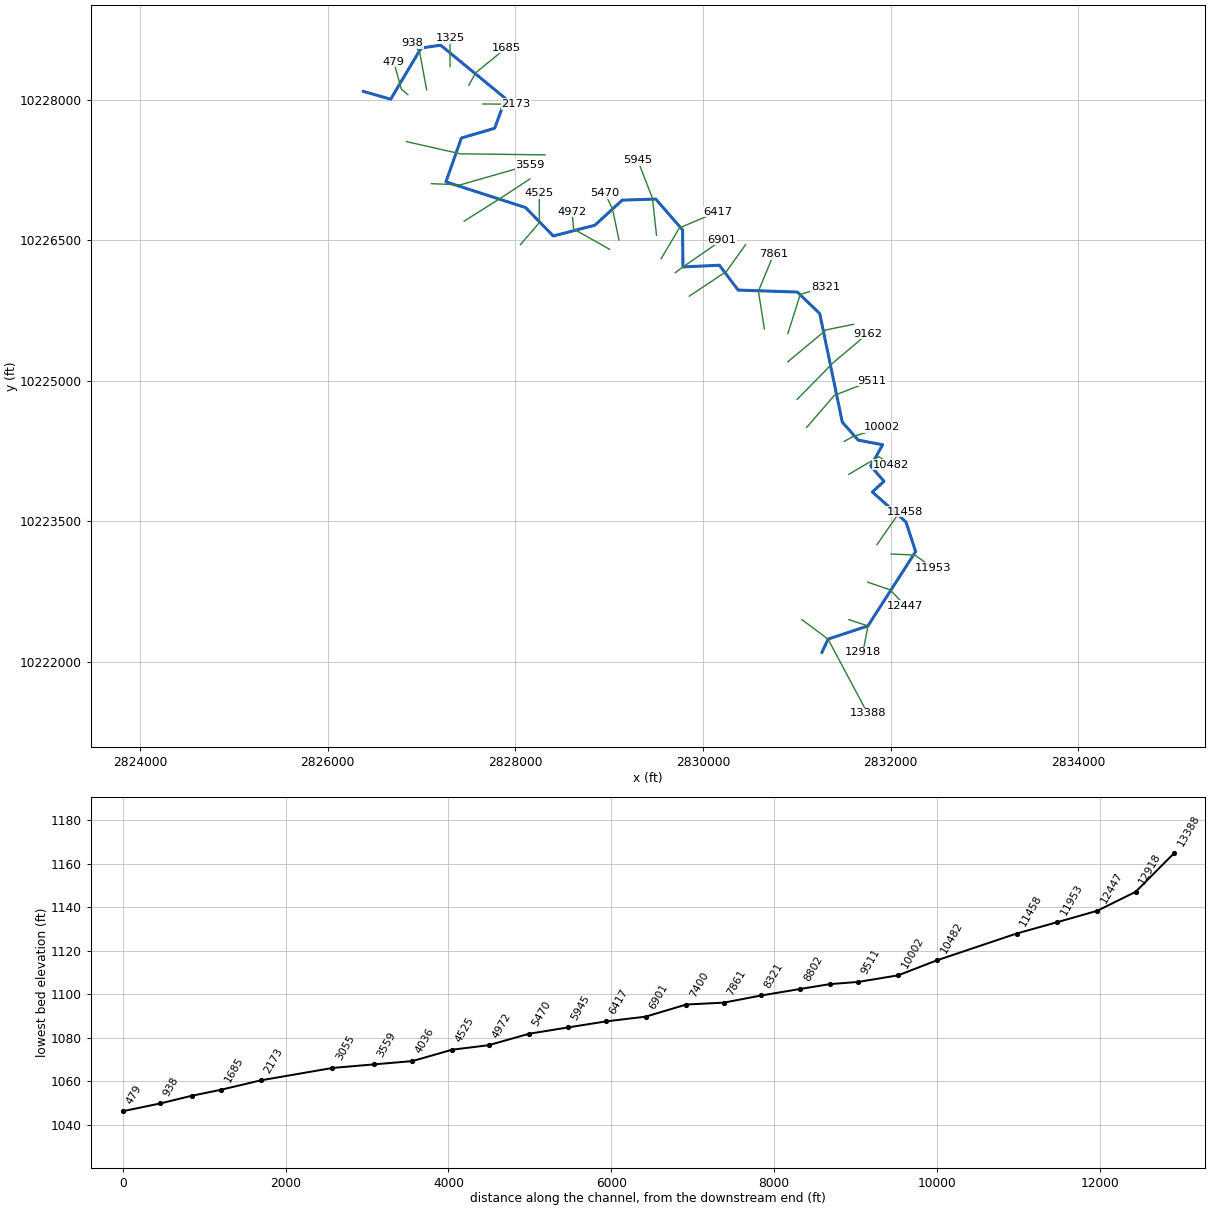
--- LITTLE LLANO 027.prj (project) ---

Proj Title=LITTLE LLANO 027 Base Level Engineering
Current Plan=p01
Default Exp/Contr=0.3,0.1
English Units
Geom File=g01
Flow File=f01
Plan File=p01
BEGIN DESCRIPTION:
LITTLE LLANO 027
END DESCRIPTION:

--- LITTLE LLANO 027.p01 (plan) ---

Plan Title=Multiple Run
Short Identifier=Multiple
Geom File=g01
Flow File=f01
Subcritical Flow
K Sum by GR= 0
Std Step Tol= 0.01
Critical Tol= 0.01
Num of Std Step Trials= 20
Max Error Tol= 0.3
Flow Tol Ratio= 0.001
Split Flow NTrial= 30
Split Flow Tol= 0.02
Split Flow Ratio= 0.02
Log Output Level= 0
Friction Slope Method= 1
Unsteady Friction Slope Method= 2
Unsteady Bridges Friction Slope Method= 1
Parabolic Critical Depth
Global Vel Dist=  1 , 1 , 1
Global Log Level= 0
CheckData=True
Encroach Param= -1, 0, 0, 0
BEGIN DESCRIPTION:
Multiple Run
END DESCRIPTION:

--- LITTLE LLANO 027.f01 (steady flow) ---

Flow Title=Multiple
Number of Profiles=7
Profile Names=10-year,25-year,50-year,1pct_min,100-year,1pct_plu,500-year
River Rch & RM= LITTLE LLANO 027,Reach-1,13388
      26      37      51      24      72     216     161
River Rch & RM= LITTLE LLANO 027,Reach-1,10002
     143     302     494     266     803    2426    2258
River Rch & RM= LITTLE LLANO 027,Reach-1,5470
     156     335     550     297     898    2711    2541
Boundary for River Rch & Prof#=LITTLE LLANO 027,Reach-1,1
Up Type=0
Dn Type=3
Dn Slope=0.005
Boundary for River Rch & Prof#=LITTLE LLANO 027,Reach-1,2
Up Type=0
Dn Type=3
Dn Slope=0.005
Boundary for River Rch & Prof#=LITTLE LLANO 027,Reach-1,3
Up Type=0
Dn Type=3
Dn Slope=0.005
Boundary for River Rch & Prof#=LITTLE LLANO 027,Reach-1,4
Up Type=0
Dn Type=3
Dn Slope=0.005
Boundary for River Rch & Prof#=LITTLE LLANO 027,Reach-1,5
Up Type=0
Dn Type=3
Dn Slope=0.005
Boundary for River Rch & Prof#=LITTLE LLANO 027,Reach-1,6
Up Type=0
Dn Type=3
Dn Slope=0.005
Boundary for River Rch & Prof#=LITTLE LLANO 027,Reach-1,7
Up Type=0
Dn Type=3
Dn Slope=0.005

--- LITTLE LLANO 027.g01 (geometry) ---

Geom Title=Existing Conditions

River Reach=LITTLE LLANO 027,Reach-1
Reach XY= 30
      2831269.50     10222104.00      2831334.00     10222245.00
      2831759.25     10222386.00      2832267.75     10223179.00
      2832164.25     10223495.00      2831806.00     10223815.00
      2831930.25     10223928.00      2831789.25     10224092.00
      2831915.75     10224318.00      2831654.75     10224368.00
      2831485.75     10224560.00      2831245.50     10225718.00
      2831006.50     10225947.00      2830375.50     10225968.00
      2830176.25     10226233.00      2829787.50     10226215.00
      2829783.50     10226610.00      2829497.50     10226939.00
      2829140.00     10226927.00      2828849.25     10226660.00
      2828405.50     10226545.00      2828110.50     10226848.00
      2827261.25     10227122.00      2827426.25     10227590.00
      2827781.25     10227694.00      2827897.00     10228011.00
      2827205.25     10228580.00      2826997.25     10228550.00
      2826672.50     10228004.00      2826380.75     10228087.00

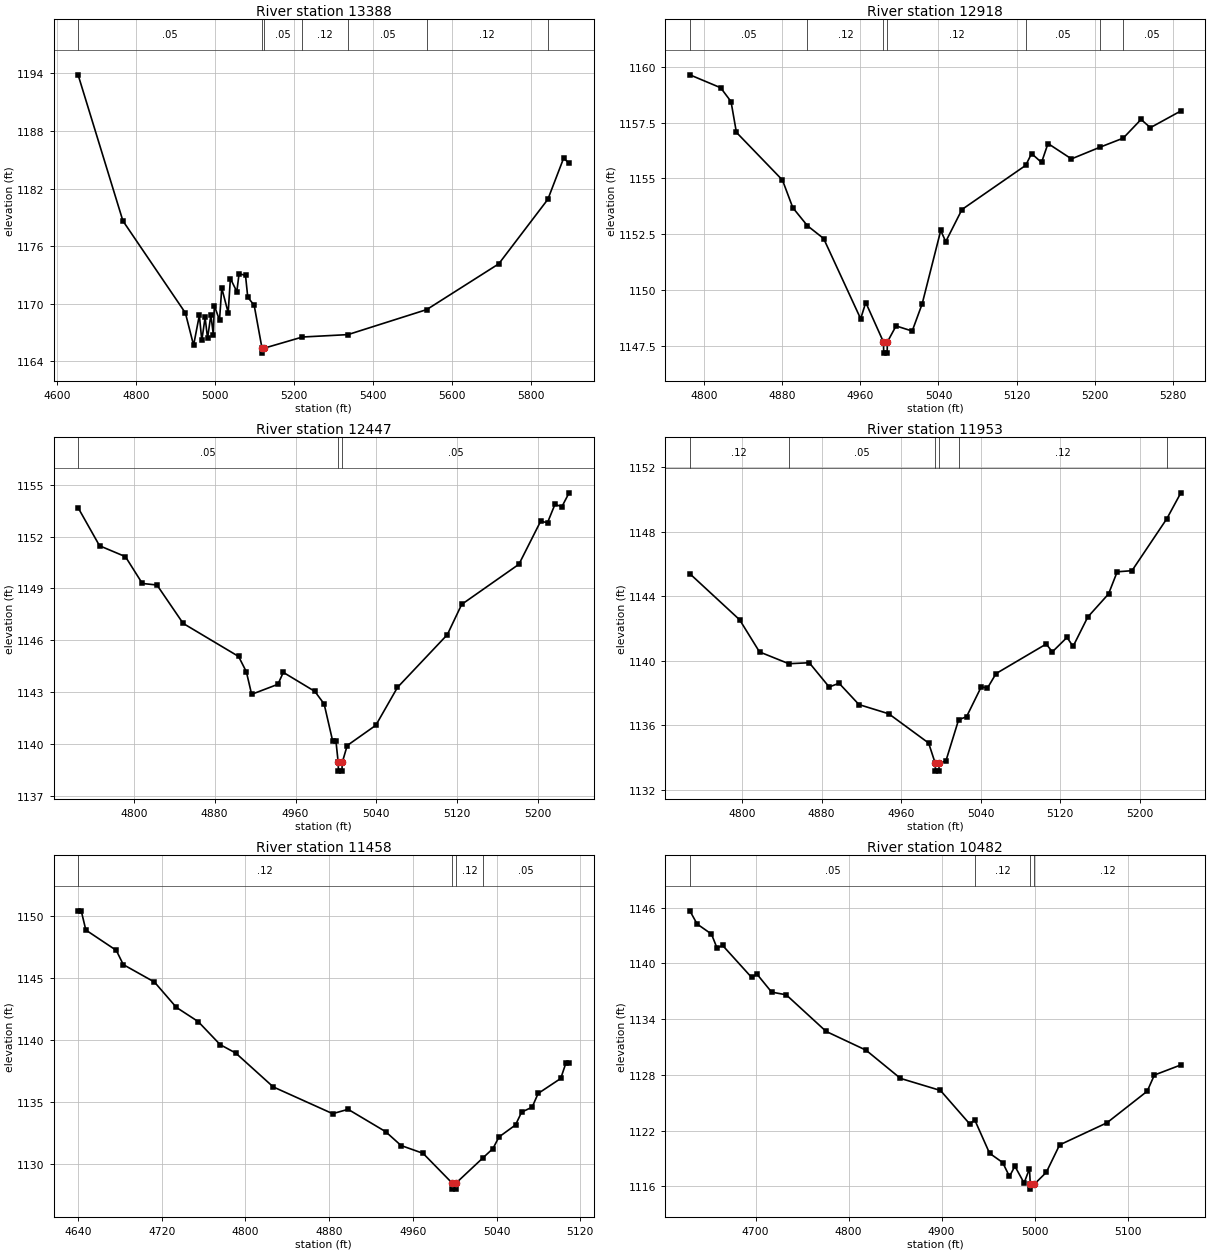
Type RM Length L Ch R = 1,13388,470,470,470
BEGIN DESCRIPTION:
LITTLE LLANO 027 28.0
END DESCRIPTION:
XS GIS Cut Line= 3
      2831055.70     10222453.10      2831334.00     10222245.00
      2831755.70     10221453.08
#Sta/Elev= 30
  4652.5 1193.86  4766.1 1178.63  4924.5 1169.03  4945.3 1165.66  4959.9 1168.79
  4966.1 1166.17  4974.5 1168.56  4980.7 1166.38  4989.1 1168.82  4995.3 1166.78
  4997.9 1169.80  5011.0 1168.27  5016.7 1171.63  5033.0 1169.05  5038.6 1172.62
  5054.9 1171.25  5060.6 1173.13  5076.9 1172.94  5082.6 1170.68  5098.9 1169.82
  5118.8 1165.34  5119.1 1164.84  5122.8 1165.34  5221.2 1166.52  5336.5 1166.77
  5536.3 1169.38  5718.9 1174.15  5843.4 1180.88  5883.3 1185.16  5897.2 1184.65
#Mann=7,-1,0
  4652.5    0.05       0  5118.8    0.05       0  5122.8    0.05       0
  5221.2    0.12       0  5336.5    0.05       0  5536.3    0.12       0
  5843.4    0.05       0
Bank Sta=5118.8,5122.8
Exp/Cntr=0.3,0.1

Type RM Length L Ch R = 1,12918,471,471,471
BEGIN DESCRIPTION:
LITTLE LLANO 027 27.0
END DESCRIPTION:
XS GIS Cut Line= 3
      2831555.73     10222453.10      2831759.25     10222386.00
      2831705.69     10222103.13
#Sta/Elev= 30
  4785.7 1159.64  4817.2 1159.06  4827.8 1158.44  4833.3 1157.06  4880.4 1154.92
  4891.0 1153.68  4906.0 1152.87  4922.5 1152.30  4960.4 1148.70  4965.6 1149.43
  4983.7 1147.66  4984.0 1147.16  4987.5 1147.16  4987.7 1147.66  4996.6 1148.38
  5013.1 1148.15  5023.3 1149.37  5042.3 1152.66  5047.4 1152.16  5064.0 1153.60
  5129.2 1155.58  5135.2 1156.11  5145.4 1155.71  5152.0 1156.56  5176.0 1155.87
  5205.5 1156.40  5228.9 1156.80  5247.2 1157.64  5256.7 1157.27  5287.9 1158.02
#Mann=7,-1,0
  4785.7    0.05       0  4906.0    0.12       0  4983.7    0.07       0
  4987.7    0.12       0  5129.2    0.05       0  5205.5    0.12       0
  5228.9    0.05       0
Bank Sta=4983.7,4987.7
Exp/Cntr=0.3,0.1

Type RM Length L Ch R = 1,12447,494,494,494
BEGIN DESCRIPTION:
LITTLE LLANO 027 26.0
END DESCRIPTION:
XS GIS Cut Line= 3
      2831755.68     10222853.11      2831996.75     10222770.00
      2832155.71     10222603.08
#Sta/Elev= 30
  4745.0 1153.67  4766.2 1151.47  4791.8 1150.84  4808.5 1149.29  4823.0 1149.20
  4848.9 1146.98  4903.7 1145.07  4911.4 1144.18  4916.6 1142.88  4942.6 1143.46
  4947.9 1144.15  4979.1 1143.05  4988.3 1142.32  4996.8 1140.16  5000.0 1140.16
  5002.2 1138.94  5002.4 1138.44  5005.9 1138.44  5006.2 1138.94  5011.1 1139.92
  5039.4 1141.09  5060.8 1143.28  5110.1 1146.33  5124.3 1148.08  5180.9 1150.40
  5202.3 1152.88  5209.2 1152.81  5216.5 1153.86  5223.4 1153.73  5230.5 1154.53
#Mann=3,-1,0
  4745.0    0.05       0  5002.2    0.05       0  5006.2    0.05       0
Bank Sta=5002.2,5006.2
Exp/Cntr=0.3,0.1

Type RM Length L Ch R = 1,11953,495,495,495
BEGIN DESCRIPTION:
LITTLE LLANO 027 25.0
END DESCRIPTION:
XS GIS Cut Line= 3
      2832005.64     10223153.11      2832258.00     10223142.00
      2832455.69     10223003.11
#Sta/Elev= 30
  4747.4 1145.39  4797.5 1142.54  4817.5 1140.55  4847.0 1139.82  4867.6 1139.88
  4887.6 1138.38  4897.6 1138.61  4917.6 1137.29  4947.6 1136.72  4987.7 1134.91
  4994.3 1133.67  4994.6 1133.17  4998.1 1133.17  4998.3 1133.67  5005.0 1133.78
  5017.9 1136.35  5025.9 1136.54  5040.7 1138.39  5046.9 1138.31  5055.6 1139.21
  5106.1 1141.04  5112.2 1140.55  5127.0 1141.45  5133.1 1140.89  5147.9 1142.71
  5168.8 1144.14  5177.5 1145.51  5192.4 1145.58  5227.5 1148.80  5241.6 1150.40
#Mann=6,-1,0
  4747.4    0.12       0  4847.0    0.05       0  4994.3    0.05       0
  4998.3    0.05       0  5017.9    0.12       0  5227.5    0.05       0
Bank Sta=4994.3,4998.3
Exp/Cntr=0.3,0.1

Type RM Length L Ch R = 1,11458,976,976,976
BEGIN DESCRIPTION:
LITTLE LLANO 027 24.0
END DESCRIPTION:
XS GIS Cut Line= 3
      2831855.69     10223253.11      2832060.75     10223549.00
      2832155.71     10223603.13
#Sta/Elev= 30
  4640.0 1150.45  4643.0 1150.45  4647.4 1148.90  4676.5 1147.26  4683.2 1146.11
  4713.0 1144.70  4733.9 1142.66  4754.8 1141.51  4775.8 1139.65  4790.7 1138.97
  4826.5 1136.24  4883.3 1134.08  4898.1 1134.43  4933.9 1132.63  4948.7 1131.51
  4969.7 1130.88  4997.4 1128.49  4997.7 1127.99  5001.2 1127.99  5001.4 1128.49
  5027.3 1130.54  5036.5 1131.26  5042.3 1132.20  5058.1 1133.17  5063.9 1134.20
  5074.0 1134.61  5079.7 1135.71  5101.3 1136.92  5106.4 1138.20  5109.3 1138.20
#Mann=4,-1,0
  4640.0    0.12       0  4997.4    0.07       0  5001.4    0.12       0
  5027.3    0.05       0
Bank Sta=4997.4,5001.4
Exp/Cntr=0.3,0.1

Type RM Length L Ch R = 1,10482,480,480,480
BEGIN DESCRIPTION:
LITTLE LLANO 027 23.0
END DESCRIPTION:
XS GIS Cut Line= 3
      2831555.69     10224003.12      2831875.25     10224191.00
      2832005.70     10224103.10
#Sta/Elev= 30
  4629.3 1145.66  4637.1 1144.24  4652.5 1143.16  4658.6 1141.63  4664.4 1141.95
  4695.7 1138.49  4701.5 1138.84  4717.2 1136.91  4732.9 1136.62  4775.8 1132.68
  4818.7 1130.66  4855.8 1127.62  4898.8 1126.32  4930.1 1122.73  4935.7 1123.14
  4951.6 1119.56  4965.7 1118.56  4973.0 1117.06  4978.8 1118.17  4988.7 1116.36
  4994.5 1117.90  4995.4 1116.20  4995.6 1115.70  4999.4 1116.20  5012.6 1117.51
  5026.9 1120.46  5077.8 1122.84  5121.1 1126.24  5128.8 1127.98  5157.3 1129.07
#Mann=4,-1,0
  4629.3    0.05       0  4935.7    0.12       0  4995.4    0.07       0
  4999.4    0.12       0
Bank Sta=4995.4,4999.4
Exp/Cntr=0.3,0.1

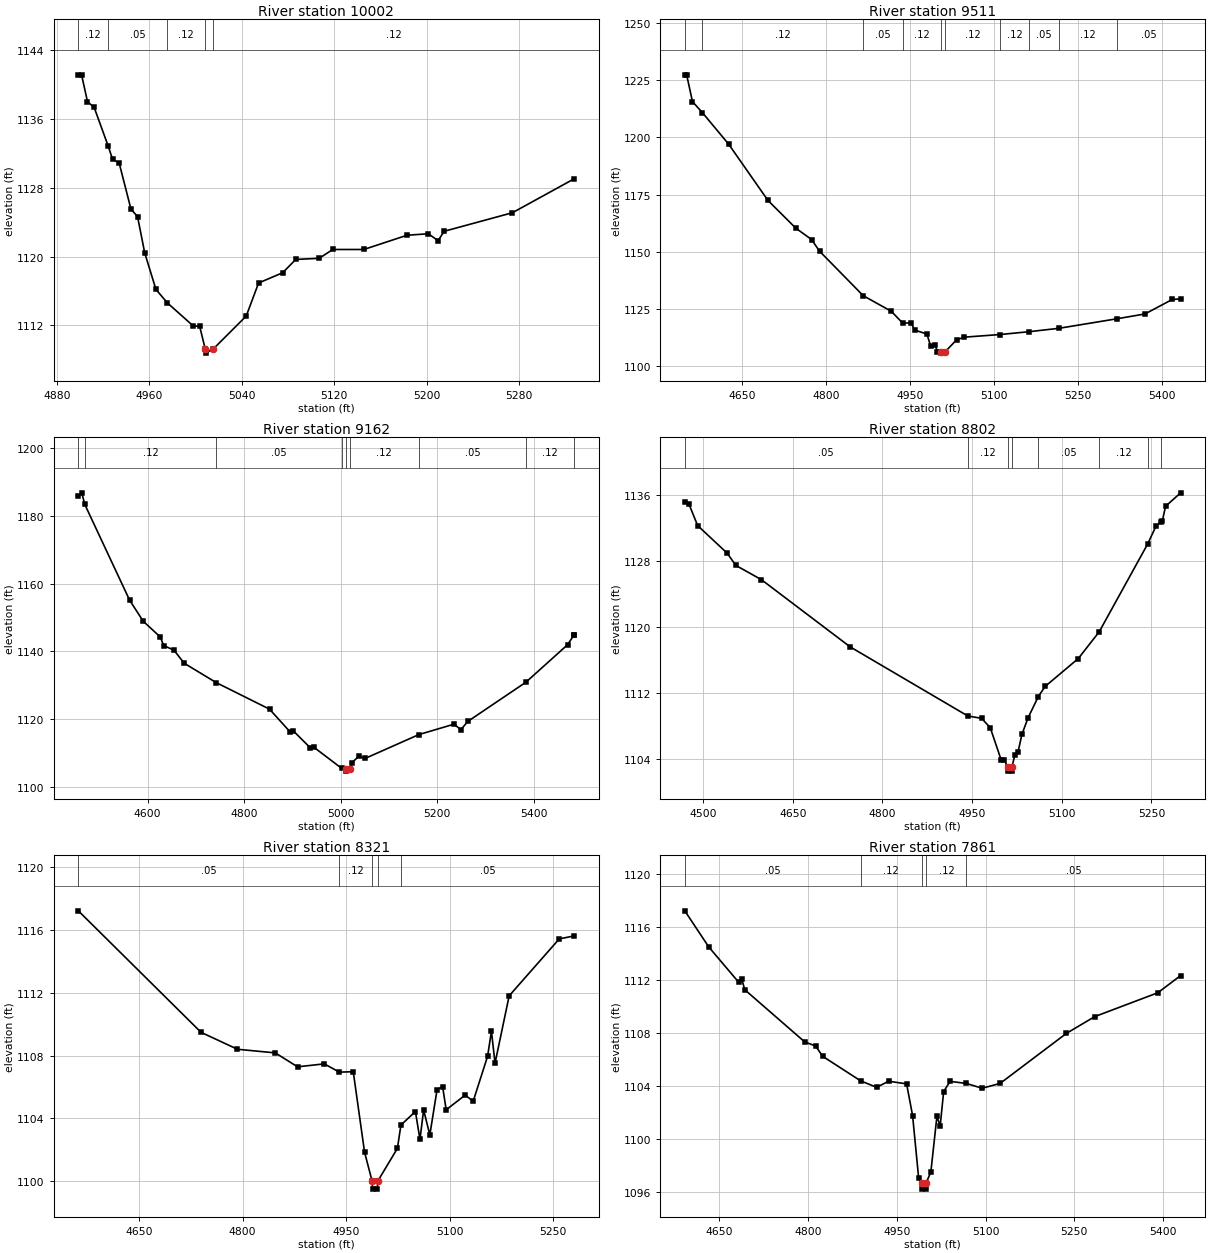
Type RM Length L Ch R = 1,10002,491,491,491
BEGIN DESCRIPTION:
LITTLE LLANO 027 22.0
END DESCRIPTION:
XS GIS Cut Line= 3
      2831505.71     10224353.13      2831594.00     10224403.00
      2831905.72     10224503.12
#Sta/Elev= 30
  4898.6 1141.16  4901.4 1141.16  4906.5 1138.04  4912.3 1137.36  4924.3 1132.91
  4928.2 1131.32  4933.9 1130.90  4944.1 1125.52  4949.8 1124.65  4956.0 1120.43
  4965.7 1116.17  4975.7 1114.59  4998.1 1111.90  5003.5 1111.90  5008.3 1109.25
  5008.8 1108.75  5015.4 1109.25  5043.8 1113.07  5054.5 1116.92  5075.3 1118.11
  5086.6 1119.66  5106.8 1119.79  5118.7 1120.82  5145.5 1120.82  5182.9 1122.48
  5201.3 1122.65  5209.7 1121.85  5215.0 1122.94  5274.0 1125.10  5327.4 1129.05
#Mann=5,-1,0
  4898.6    0.12       0  4924.3    0.05       0  4975.7    0.12       0
  5008.3    0.07       0  5015.4    0.12       0
Bank Sta=5008.3,5015.4
Exp/Cntr=0.3,0.1

Type RM Length L Ch R = 1,9511,349,349,349
BEGIN DESCRIPTION:
LITTLE LLANO 027 21.0
END DESCRIPTION:
XS GIS Cut Line= 3
      2831105.68     10224503.11      2831401.50     10224845.00
      2831805.68     10225003.11
#Sta/Elev= 30
  4547.9 1227.39  4551.2 1227.39  4561.6 1215.68  4579.2 1210.90  4626.3 1197.07
  4696.5 1172.47  4746.3 1160.34  4774.4 1155.39  4788.7 1150.29  4866.7 1130.84
  4916.9 1124.00  4937.5 1118.79  4952.1 1118.98  4958.7 1115.80  4980.6 1114.05
  4987.2 1108.83  4994.8 1109.43  4999.4 1106.39  5005.6 1106.21  5006.1 1105.71
  5012.8 1106.21  5033.7 1111.54  5047.4 1112.69  5111.9 1113.85  5162.7 1115.07
  5216.2 1116.55  5320.4 1120.74  5370.2 1122.83  5419.1 1129.18  5434.0 1129.44
#Mann=10,-1,0
  4547.9    0.05       0  4579.2    0.12       0  4866.7    0.05       0
  4937.5    0.12       0  5005.6    0.07       0  5012.8    0.12       0
  5111.9    0.12       0  5162.7    0.05       0  5216.2    0.12       0
  5320.4    0.05       0
Bank Sta=5005.6,5012.8
Exp/Cntr=0.3,0.1

Type RM Length L Ch R = 1,9162,360,360,360
BEGIN DESCRIPTION:
LITTLE LLANO 027 20.0
END DESCRIPTION:
XS GIS Cut Line= 3
      2831005.67     10224803.10      2831386.50     10225191.00
      2831755.66     10225503.09
#Sta/Elev= 30
  4456.4 1186.00  4463.5 1186.79  4469.8 1183.36  4562.5 1155.16  4590.8 1148.91
  4626.1 1144.28  4633.2 1141.74  4654.4 1140.39  4675.7 1136.52  4742.3 1130.79
  4852.4 1122.98  4894.8 1116.31  4902.0 1116.52  4937.2 1111.53  4944.4 1111.73
  5001.5 1105.56  5011.2 1105.20  5011.7 1104.70  5018.4 1105.20  5022.5 1107.10
  5036.8 1109.03  5051.1 1108.49  5161.8 1115.48  5234.6 1118.55  5248.8 1116.92
  5263.1 1119.36  5383.5 1130.93  5469.7 1141.98  5482.5 1144.73  5483.4 1144.73
#Mann=9,-1,0
  4456.4    0.05       0  4469.8    0.12       0  4742.3    0.05       0
  5001.5    0.12       0  5011.2    0.03       0  5018.4    0.12       0
  5161.8    0.05       0  5383.5    0.12       0  5482.5    0.05       0
Bank Sta=5011.2,5018.4
Exp/Cntr=0.3,0.1

Type RM Length L Ch R = 1,8802,481,481,481
BEGIN DESCRIPTION:
LITTLE LLANO 027 19.0
END DESCRIPTION:
XS GIS Cut Line= 3
      2830905.68     10225203.11      2831313.00     10225543.00
      2831605.69     10225603.11
#Sta/Elev= 30
  4469.5 1135.17  4476.7 1134.88  4491.0 1132.31  4540.4 1128.96  4554.8 1127.48
  4597.7 1125.74  4746.1 1117.58  4942.8 1109.19  4966.0 1108.90  4980.4 1107.76
  4998.5 1103.88  5003.9 1103.88  5009.3 1102.99  5009.8 1102.49  5016.1 1102.49
  5016.6 1102.99  5021.7 1104.48  5026.8 1104.80  5033.4 1106.96  5043.6 1108.96
  5060.8 1111.55  5072.1 1112.77  5127.6 1116.16  5162.6 1119.41  5243.7 1130.08
  5258.0 1132.31  5266.2 1132.76  5268.2 1132.87  5273.6 1134.65  5298.8 1136.29
#Mann=8,-1,0
  4469.5    0.05       0  4942.8    0.12       0  5009.3    0.07       0
  5016.6    0.12       0  5060.8    0.05       0  5162.6    0.12       0
  5243.7    0.05       0  5266.2    0.12       0
Bank Sta=5009.3,5016.6
Exp/Cntr=0.3,0.1

Type RM Length L Ch R = 1,8321,460,460,460
BEGIN DESCRIPTION:
LITTLE LLANO 027 18.0
END DESCRIPTION:
XS GIS Cut Line= 3
      2830905.68     10225503.10      2831037.50     10225921.00
      2831305.71     10226003.12
#Sta/Elev= 30
  4561.8 1117.23  4739.7 1109.48  4792.5 1108.40  4847.3 1108.17  4879.6 1107.28
  4918.3 1107.47  4940.2 1106.94  4960.3 1106.97  4976.7 1101.83  4987.7 1099.98
  4988.2 1099.48  4995.2 1099.48  4995.7 1099.98  5024.3 1102.08  5029.4 1103.57
  5050.4 1104.43  5057.0 1102.65  5062.3 1104.53  5071.3 1102.94  5081.8 1105.83
  5089.8 1106.02  5095.0 1104.54  5122.6 1105.48  5134.1 1105.08  5155.0 1107.95
  5160.6 1109.55  5165.8 1107.51  5186.3 1111.81  5258.9 1115.44  5280.5 1115.63
#Mann=5,-1,0
  4561.8    0.05       0  4940.2    0.12       0  4987.7    0.07       0
  4995.7    0.12       0  5029.4    0.05       0
Bank Sta=4987.7,4995.7
Exp/Cntr=0.3,0.1

Type RM Length L Ch R = 1,7861,461,461,461
BEGIN DESCRIPTION:
LITTLE LLANO 027 17.0
END DESCRIPTION:
XS GIS Cut Line= 3
      2830655.69     10225553.10      2830592.00     10225956.00
      2830755.68     10226353.09
#Sta/Elev= 30
  4592.1 1117.20  4632.6 1114.47  4683.2 1111.80  4688.2 1112.06  4693.4 1111.24
  4794.6 1107.30  4813.0 1106.99  4825.0 1106.21  4889.0 1104.36  4916.1 1103.87
  4936.3 1104.33  4966.7 1104.13  4976.8 1101.74  4987.0 1097.05  4992.0 1096.68
  4992.5 1096.18  4999.6 1096.18  5000.1 1096.68  5007.7 1097.49  5017.9 1101.68
  5023.4 1100.95  5029.3 1103.55  5040.1 1104.32  5067.8 1104.16  5094.2 1103.80
  5124.5 1104.16  5236.5 1107.94  5284.4 1109.21  5390.9 1111.01  5429.5 1112.31
#Mann=5,-1,0
  4592.1    0.05       0  4889.0    0.12       0  4992.0    0.07       0
  5000.1    0.12       0  5067.8    0.05       0
Bank Sta=4992,5000.1
Exp/Cntr=0.3,0.1

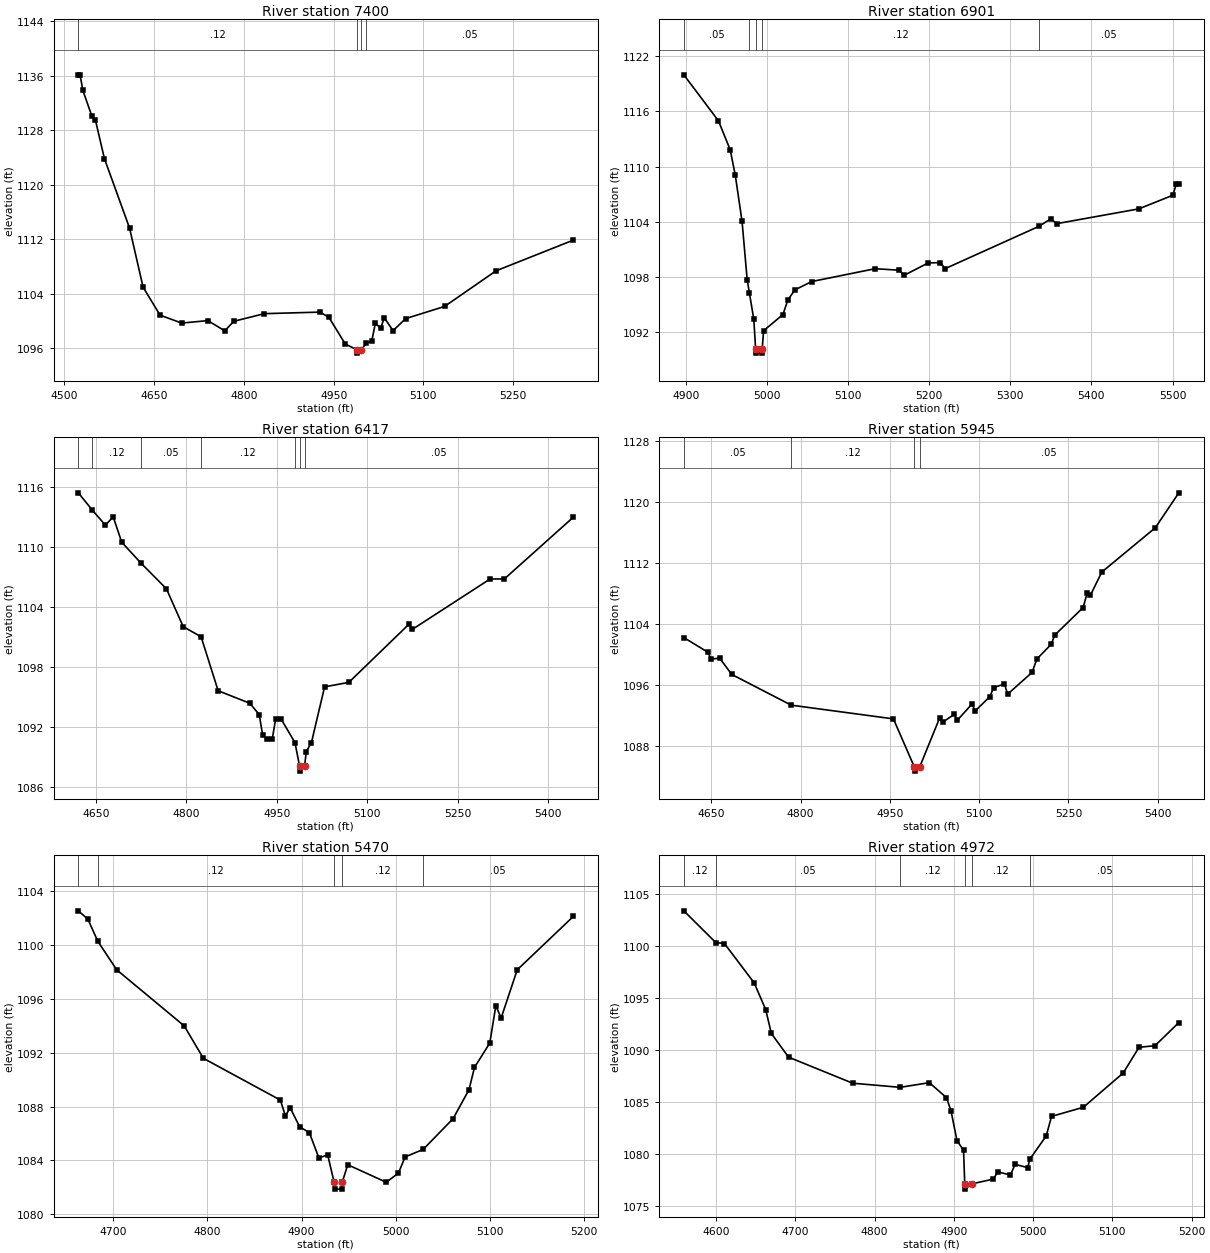
Type RM Length L Ch R = 1,7400,499,499,499
BEGIN DESCRIPTION:
LITTLE LLANO 027 16.0
END DESCRIPTION:
XS GIS Cut Line= 3
      2829855.67     10225903.11      2830252.00     10226168.00
      2830455.69     10226453.12
#Sta/Elev= 30
  4523.3 1136.16  4526.3 1136.16  4530.8 1133.92  4545.8 1130.14  4551.8 1129.57
  4566.9 1123.88  4608.9 1113.69  4631.6 1104.99  4660.0 1100.89  4696.0 1099.73
  4739.8 1100.09  4768.1 1098.59  4783.1 1099.99  4834.1 1101.11  4927.2 1101.34
  4942.2 1100.56  4969.3 1096.67  4988.4 1095.82  4988.9 1095.32  4996.5 1095.82
  5004.3 1096.77  5013.7 1097.09  5019.8 1099.77  5028.4 1098.95  5034.6 1100.51
  5049.3 1098.62  5070.2 1100.38  5135.3 1102.17  5221.4 1107.40  5350.4 1111.90
#Mann=4,-1,0
  4523.3    0.12       0  4988.4    0.07       0  4996.5    0.12       0
  5004.3    0.05       0
Bank Sta=4988.4,4996.5
Exp/Cntr=0.3,0.1

Type RM Length L Ch R = 1,6901,484,484,484
BEGIN DESCRIPTION:
LITTLE LLANO 027 15.0
END DESCRIPTION:
XS GIS Cut Line= 3
      2829705.67     10226153.10      2829787.50     10226215.00
      2830205.66     10226503.10
#Sta/Elev= 30
  4897.4 1119.96  4940.1 1114.96  4954.6 1111.81  4960.9 1109.03  4969.2 1104.03
  4975.5 1097.71  4978.2 1096.29  4983.7 1093.39  4985.9 1090.23  4986.4 1089.73
  4993.6 1089.73  4994.1 1090.23  4995.7 1092.16  5019.6 1093.92  5025.6 1095.48
  5034.2 1096.60  5055.4 1097.51  5133.2 1098.90  5162.9 1098.74  5169.0 1098.18
  5198.8 1099.53  5213.7 1099.56  5219.7 1098.91  5335.0 1103.49  5350.0 1104.32
  5357.0 1103.79  5458.5 1105.40  5500.4 1106.88  5504.8 1108.14  5507.8 1108.14
#Mann=5,-1,0
  4897.4    0.05       0  4978.2    0.12       0  4985.9    0.07       0
  4994.1    0.12       0  5335.0    0.05       0
Bank Sta=4985.9,4994.1
Exp/Cntr=0.3,0.1

Type RM Length L Ch R = 1,6417,472,472,472
BEGIN DESCRIPTION:
LITTLE LLANO 027 14.0
END DESCRIPTION:
XS GIS Cut Line= 3
      2829555.71     10226303.15      2829748.75     10226630.00
      2830155.66     10226803.10
#Sta/Elev= 30
  4620.4 1115.41  4643.3 1113.71  4665.3 1112.18  4678.4 1113.00  4692.5 1110.47
  4724.8 1108.36  4766.7 1105.81  4794.6 1102.02  4824.3 1101.01  4852.6 1095.61
  4905.2 1094.36  4920.8 1093.22  4926.6 1091.14  4933.9 1090.77  4942.3 1090.75
  4948.1 1092.80  4957.2 1092.77  4980.1 1090.43  4987.8 1088.07  4988.3 1087.57
  4996.1 1088.07  4998.9 1089.52  5007.5 1090.43  5029.3 1096.00  5069.6 1096.45
  5169.6 1102.28  5175.0 1101.75  5304.1 1106.79  5327.7 1106.79  5442.2 1112.97
#Mann=7,-1,0
  4620.4    0.05       0  4643.3    0.12       0  4724.8    0.05       0
  4824.3    0.12       0  4980.1    0.05       0  4987.8    0.05       0
  4996.1    0.05       0
Bank Sta=4987.8,4996.1
Exp/Cntr=0.3,0.1

Type RM Length L Ch R = 1,5945,475,475,475
BEGIN DESCRIPTION:
LITTLE LLANO 027 13.0
END DESCRIPTION:
XS GIS Cut Line= 3
      2829505.68     10226553.13      2829462.75     10226947.00
      2829305.69     10227353.09
#Sta/Elev= 30
  4603.8 1102.27  4644.0 1100.36  4649.5 1099.47  4664.1 1099.56  4684.3 1097.44
  4784.2 1093.41  4955.9 1091.61  4991.3 1085.26  4991.8 1084.76  4999.8 1085.26
  5033.4 1091.70  5038.8 1091.18  5058.0 1092.20  5063.3 1091.43  5087.9 1093.56
  5093.3 1092.65  5117.9 1094.53  5124.5 1095.72  5142.5 1096.19  5147.8 1094.85
  5188.8 1097.70  5197.0 1099.47  5221.0 1101.39  5226.9 1102.59  5274.6 1106.21
  5281.5 1108.13  5286.8 1107.81  5306.0 1110.86  5395.9 1116.67  5435.4 1121.25
#Mann=4,-1,0
  4603.8    0.05       0  4784.2    0.12       0  4991.3    0.05       0
  4999.8    0.05       0
Bank Sta=4991.3,4999.8
Exp/Cntr=0.3,0.1

Type RM Length L Ch R = 1,5470,498,498,498
BEGIN DESCRIPTION:
LITTLE LLANO 027 12.0
END DESCRIPTION:
XS GIS Cut Line= 3
      2829105.68     10226503.13      2829036.75     10226833.00
      2828955.70     10227003.08
#Sta/Elev= 30
  4663.0 1102.53  4673.2 1101.91  4683.7 1100.27  4703.8 1098.15  4775.4 1093.99
  4795.8 1091.58  4877.5 1088.48  4882.8 1087.31  4887.9 1087.91  4898.0 1086.49
  4908.2 1086.07  4918.4 1084.18  4927.7 1084.42  4934.6 1082.37  4935.1 1081.87
  4942.6 1081.87  4943.1 1082.37  4949.0 1083.68  4989.9 1082.38  5002.8 1083.06
  5009.9 1084.26  5029.1 1084.82  5060.8 1087.10  5077.7 1089.25  5083.5 1090.90
  5099.8 1092.72  5106.2 1095.49  5111.8 1094.57  5128.9 1098.15  5188.4 1102.11
#Mann=5,-1,0
  4663.0    0.05       0  4683.7    0.12       0  4934.6    0.07       0
  4943.1    0.12       0  5029.1    0.05       0
Bank Sta=4934.6,4943.1
Exp/Cntr=0.3,0.1

Type RM Length L Ch R = 1,4972,447,447,447
BEGIN DESCRIPTION:
LITTLE LLANO 027 11.0
END DESCRIPTION:
XS GIS Cut Line= 3
      2829005.65     10226403.13      2828622.00     10226620.00
      2828605.69     10226803.07
#Sta/Elev= 30
  4559.3 1103.42  4599.6 1100.36  4610.5 1100.27  4648.1 1096.47  4662.6 1093.90
  4669.7 1091.60  4691.4 1089.32  4772.2 1086.81  4832.2 1086.41  4869.0 1086.86
  4890.6 1085.42  4896.3 1084.17  4903.9 1081.28  4912.2 1080.34  4913.7 1077.10
  4914.2 1076.60  4922.3 1077.10  4949.8 1077.57  4955.5 1078.26  4971.4 1077.96
  4977.2 1078.99  4993.1 1078.67  4995.9 1079.49  5016.5 1081.73  5023.2 1083.61
  5063.4 1084.49  5113.6 1087.79  5133.6 1090.27  5153.7 1090.42  5183.8 1092.65
#Mann=6,-1,0
  4559.3    0.12       0  4599.6    0.05       0  4832.2    0.12       0
  4913.7    0.03       0  4922.3    0.12       0  4995.9    0.05       0
Bank Sta=4913.7,4922.3
Exp/Cntr=0.3,0.1

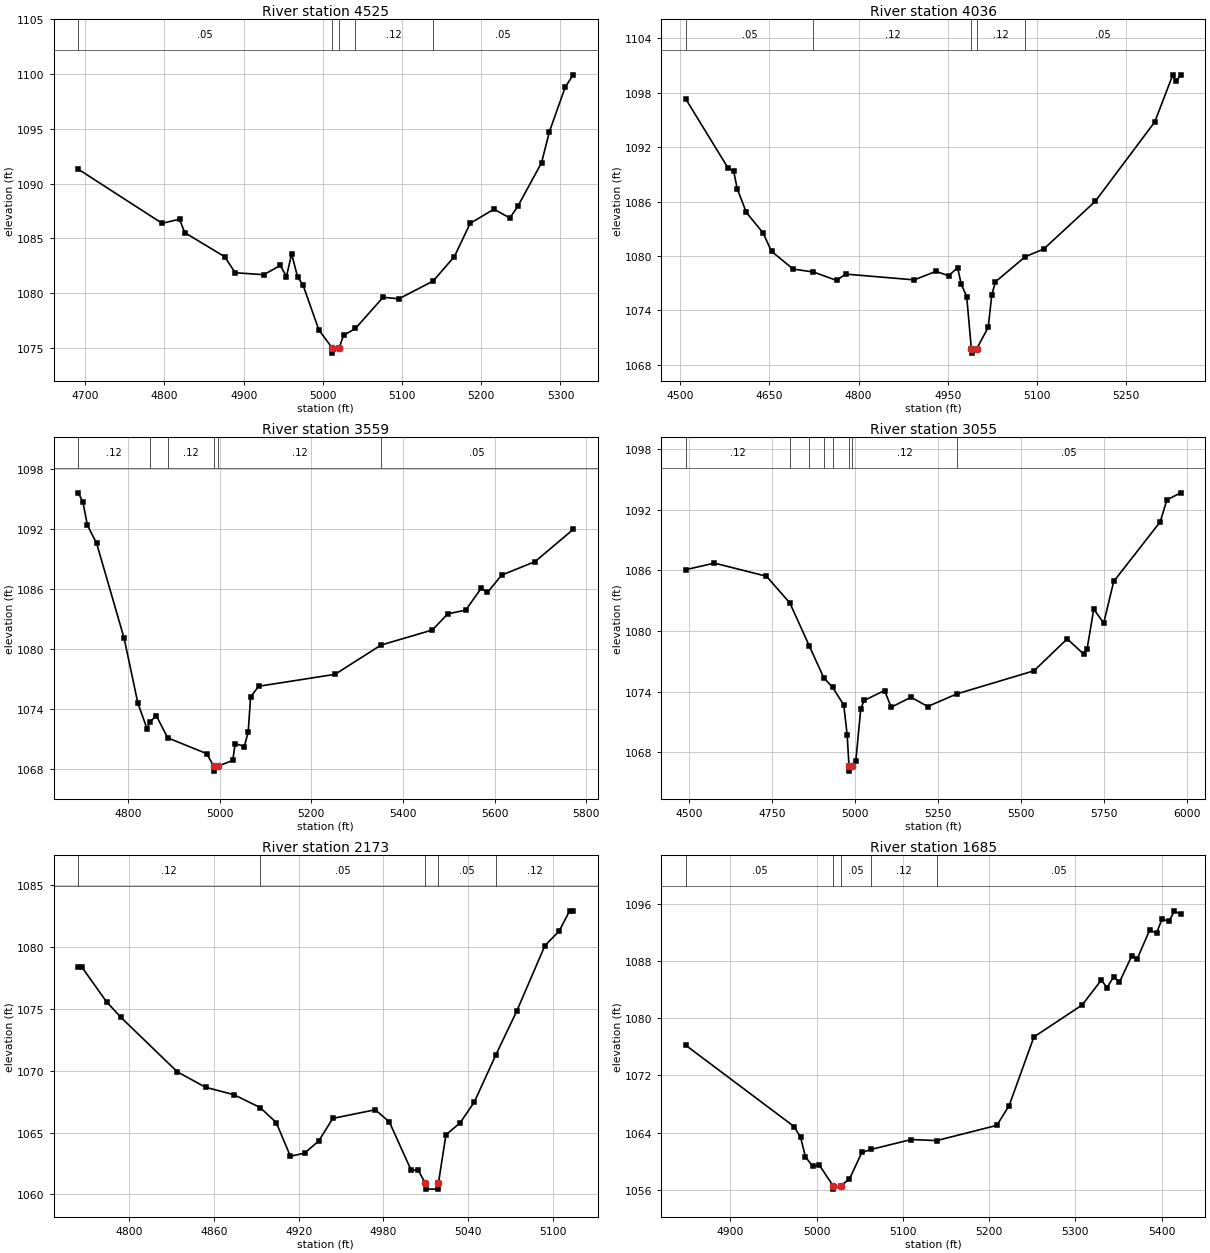
Type RM Length L Ch R = 1,4525,489,489,489
BEGIN DESCRIPTION:
LITTLE LLANO 027 10.0
END DESCRIPTION:
XS GIS Cut Line= 3
      2828055.66     10226453.08      2828257.25     10226687.00
      2828255.68     10227003.10
#Sta/Elev= 30
  4691.2 1091.32  4797.1 1086.38  4819.0 1086.76  4825.6 1085.53  4876.1 1083.33
  4889.3 1081.87  4925.5 1081.69  4946.3 1082.54  4954.0 1081.52  4960.6 1083.58
  4968.2 1081.46  4974.8 1080.78  4995.0 1076.64  5011.5 1075.03  5012.0 1074.53
  5020.7 1075.03  5026.1 1076.15  5041.1 1076.78  5076.1 1079.63  5096.1 1079.49
  5139.4 1081.12  5166.1 1083.35  5186.1 1086.39  5216.1 1087.67  5236.1 1086.87
  5246.1 1087.93  5276.1 1091.91  5286.1 1094.76  5306.1 1098.83  5316.1 1099.94
#Mann=5,-1,0
  4691.2    0.05       0  5011.5    0.03       0  5020.7    0.05       0
  5041.1    0.12       0  5139.4    0.05       0
Bank Sta=5011.5,5020.7
Exp/Cntr=0.3,0.1

Type RM Length L Ch R = 1,4036,477,477,477
BEGIN DESCRIPTION:
LITTLE LLANO 027 9.0
END DESCRIPTION:
XS GIS Cut Line= 3
      2827455.66     10226703.09      2827870.50     10226965.00
      2828155.65     10227153.09
#Sta/Elev= 30
  4509.4 1097.33  4580.6 1089.70  4590.0 1089.36  4595.9 1087.44  4611.2 1084.82
  4639.5 1082.54  4653.6 1080.52  4690.1 1078.56  4724.1 1078.24  4763.0 1077.31
  4778.3 1078.01  4893.6 1077.37  4930.1 1078.31  4951.3 1077.83  4966.6 1078.71
  4972.5 1076.91  4981.8 1075.53  4989.6 1069.79  4990.1 1069.29  4998.8 1069.79
  5018.0 1072.14  5024.0 1075.73  5030.2 1077.16  5080.3 1079.93  5111.3 1080.77
  5197.9 1086.03  5298.0 1094.79  5328.1 1099.94  5334.1 1099.29  5341.6 1099.99
#Mann=5,-1,0
  4509.4    0.05       0  4724.1    0.12       0  4989.6    0.07       0
  4998.8    0.12       0  5080.3    0.05       0
Bank Sta=4989.6,4998.8
Exp/Cntr=0.3,0.1

Type RM Length L Ch R = 1,3559,504,504,504
BEGIN DESCRIPTION:
LITTLE LLANO 027 8.0
END DESCRIPTION:
XS GIS Cut Line= 3
      2827105.68     10227103.11      2827414.00     10227090.00
      2828155.69     10227303.11
#Sta/Elev= 30
  4691.4 1095.60  4701.4 1094.69  4711.4 1092.35  4731.4 1090.55  4791.5 1081.04
  4821.5 1074.55  4841.5 1072.00  4848.5 1072.71  4861.6 1073.31  4886.5 1071.09
  4971.7 1069.51  4987.0 1068.26  4987.5 1067.76  4996.3 1068.26  5028.6 1068.83
  5033.8 1070.52  5053.8 1070.22  5062.3 1071.68  5067.5 1075.17  5085.0 1076.25
  5251.7 1077.44  5352.2 1080.37  5464.3 1081.88  5498.0 1083.50  5537.0 1083.86
  5570.7 1086.04  5584.4 1085.63  5615.6 1087.37  5688.5 1088.72  5771.7 1091.94
#Mann=6,-1,0
  4691.4    0.12       0  4848.5    0.05       0  4886.5    0.12       0
  4987.0    0.07       0  4996.3    0.12       0  5352.2    0.05       0
Bank Sta=4987,4996.3
Exp/Cntr=0.3,0.1

Type RM Length L Ch R = 1,3055,882,882,882
BEGIN DESCRIPTION:
Mapping XS 053fd746
END DESCRIPTION:
XS GIS Cut Line= 3
      2826841.64     10227551.34      2827416.68     10227421.15
      2828317.32     10227410.30
#Sta/Elev= 30
  4489.9 1086.05  4576.1 1086.70  4733.0 1085.40  4803.3 1082.76  4862.5 1078.47
  4905.5 1075.36  4932.0 1074.42  4965.7 1072.67  4975.9 1069.72  4981.5 1066.63
  4982.0 1066.13  4990.8 1066.63  5002.1 1067.18  5017.0 1072.32  5027.2 1073.12
  5088.5 1074.10  5108.5 1072.45  5168.5 1073.44  5218.5 1072.52  5306.6 1073.77
  5538.5 1076.05  5638.5 1079.21  5688.5 1077.69  5698.5 1078.24  5718.5 1082.14
  5748.5 1080.78  5778.6 1084.89  5918.6 1090.78  5938.6 1092.95  5980.2 1093.65
#Mann=8,-1,0
  4489.9    0.12       0  4803.3    0.05       0  4862.5    0.12       0
  4905.5    0.05       0  4932.0    0.12       0  4981.5    0.07       0
  4990.8    0.12       0  5306.6    0.05       0
Bank Sta=4981.5,4990.8
Exp/Cntr=0.3,0.1

Type RM Length L Ch R = 1,2173,488,488,488
BEGIN DESCRIPTION:
LITTLE LLANO 027 5.0
END DESCRIPTION:
XS GIS Cut Line= 3
      2827655.71     10227953.11      2827891.50     10227951.00
      2828005.68     10227953.11
#Sta/Elev= 30
  4764.2 1078.38  4766.7 1078.38  4784.2 1075.57  4794.2 1074.33  4834.2 1069.91
  4854.2 1068.66  4874.2 1068.06  4892.8 1067.02  4904.2 1065.80  4914.2 1063.08
  4924.2 1063.33  4934.2 1064.31  4944.2 1066.14  4974.2 1066.84  4984.2 1065.85
  4999.6 1061.95  5004.6 1061.95  5009.5 1060.92  5010.0 1060.42  5018.4 1060.42
  5018.9 1060.92  5024.2 1064.81  5034.2 1065.78  5044.2 1067.45  5059.3 1071.23
  5074.2 1074.80  5094.2 1080.12  5104.2 1081.28  5111.7 1082.93  5114.2 1082.93
#Mann=5,-1,0
  4764.2    0.12       0  4892.8    0.05       0  5009.5    0.05       0
  5018.9    0.05       0  5059.3    0.12       0
Bank Sta=5009.5,5018.9
Exp/Cntr=0.3,0.1

Type RM Length L Ch R = 1,1685,360,360,360
BEGIN DESCRIPTION:
LITTLE LLANO 027 4.0
END DESCRIPTION:
XS GIS Cut Line= 3
      2827505.66     10228153.07      2827578.75     10228286.00
      2827905.70     10228553.13
#Sta/Elev= 30
  4848.3 1076.22  4973.9 1064.85  4981.4 1063.36  4987.1 1060.61  4995.5 1059.27
  5002.9 1059.50  5019.0 1056.59  5019.5 1056.09  5028.4 1056.59  5038.1 1057.50
  5052.5 1061.22  5063.3 1061.65  5109.9 1063.03  5139.2 1062.88  5209.0 1065.01
  5223.3 1067.78  5252.0 1077.38  5308.0 1081.86  5330.3 1085.36  5336.7 1084.27
  5344.6 1085.81  5351.1 1085.01  5365.5 1088.73  5371.9 1088.34  5386.3 1092.35
  5394.2 1091.90  5400.6 1093.89  5408.5 1093.54  5415.0 1095.03  5422.2 1094.53
#Mann=5,-1,0
  4848.3    0.05       0  5019.0    0.05       0  5028.4    0.05       0
  5063.3    0.12       0  5139.2    0.05       0
Bank Sta=5019,5028.4
Exp/Cntr=0.3,0.1

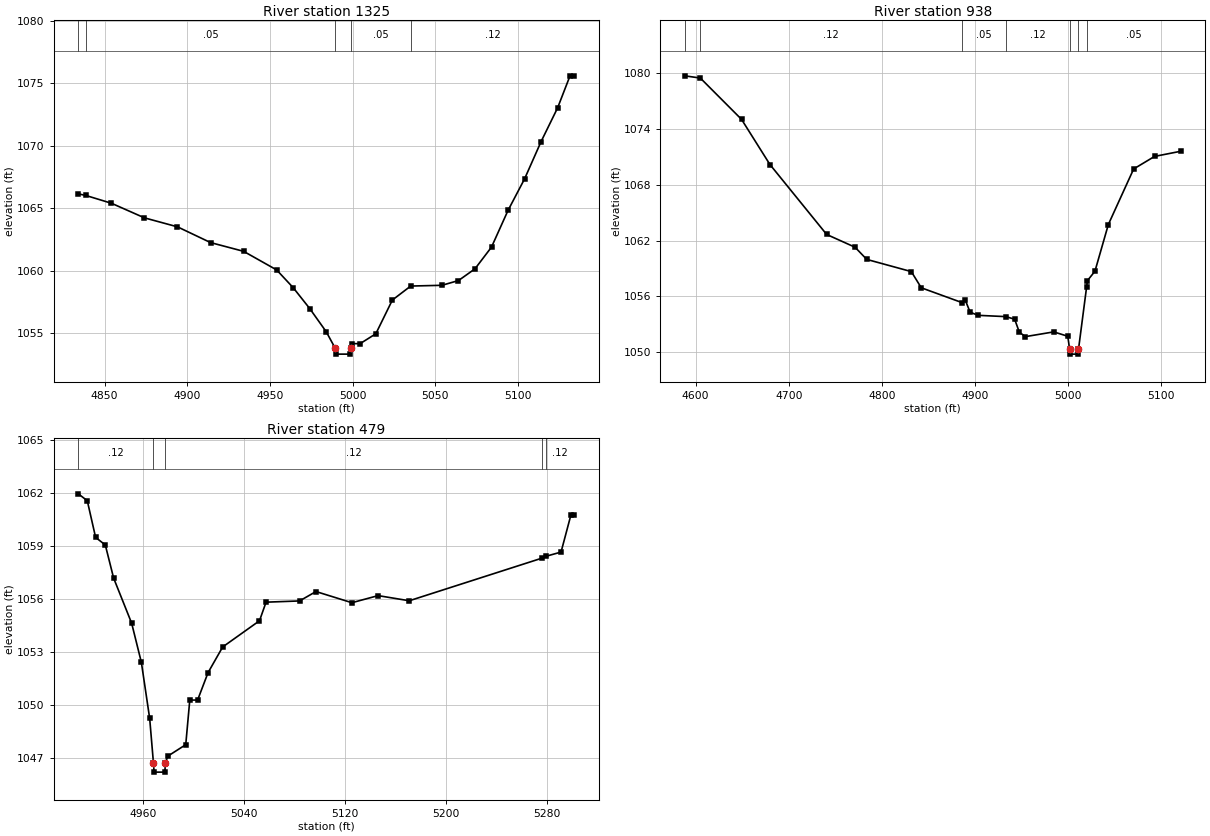
Type RM Length L Ch R = 1,1325,387,387,387
BEGIN DESCRIPTION:
LITTLE LLANO 027 3.0
END DESCRIPTION:
XS GIS Cut Line= 3
      2827305.68     10228353.10      2827304.50     10228519.00
      2827305.68     10228653.09
#Sta/Elev= 30
  4834.1 1066.15  4838.7 1066.02  4854.1 1065.40  4874.1 1064.23  4894.1 1063.51
  4914.1 1062.25  4934.1 1061.55  4954.1 1060.06  4964.1 1058.64  4974.1 1056.97
  4984.1 1055.11  4989.4 1053.82  4989.9 1053.32  4998.4 1053.32  4998.9 1053.82
  4999.6 1054.16  5004.6 1054.16  5014.1 1054.95  5024.1 1057.65  5035.2 1058.77
  5054.1 1058.83  5064.1 1059.21  5074.1 1060.15  5084.1 1061.89  5094.1 1064.83
  5104.1 1067.35  5114.1 1070.34  5124.1 1073.04  5131.6 1075.60  5134.1 1075.60
#Mann=5,-1,0
  4834.1    0.12       0  4838.7    0.05       0  4989.4    0.05       0
  4998.9    0.05       0  5035.2    0.12       0
Bank Sta=4989.4,4998.9
Exp/Cntr=0.3,0.1

Type RM Length L Ch R = 1,938,459,459,459
BEGIN DESCRIPTION:
LITTLE LLANO 027 2.0
END DESCRIPTION:
XS GIS Cut Line= 3
      2827055.68     10228103.13      2826981.00     10228508.00
      2826905.70     10228603.10
#Sta/Elev= 30
  4588.3 1079.70  4605.0 1079.46  4649.3 1075.02  4679.8 1070.17  4740.8 1062.65
  4771.3 1061.28  4783.9 1059.97  4831.8 1058.66  4842.5 1056.92  4886.5 1055.32
  4889.9 1055.57  4895.0 1054.30  4903.5 1053.96  4933.5 1053.82  4942.9 1053.54
  4947.9 1052.15  4954.4 1051.67  4984.9 1052.18  5000.0 1051.71  5002.0 1050.29
  5002.5 1049.79  5011.0 1049.79  5011.5 1050.29  5020.2 1056.98  5021.1 1057.69
  5029.2 1058.70  5043.6 1063.72  5070.8 1069.69  5093.3 1071.04  5121.3 1071.59
#Mann=7,-1,0
  4588.3    0.05       0  4605.0    0.12       0  4886.5    0.05       0
  4933.5    0.12       0  5002.0    0.07       0  5011.5    0.12       0
  5020.2    0.05       0
Bank Sta=5002,5011.5
Exp/Cntr=0.3,0.1

Type RM Length L Ch R = 1,479,0,0,0
BEGIN DESCRIPTION:
LITTLE LLANO 027 1.0
END DESCRIPTION:
XS GIS Cut Line= 3
      2826855.66     10228053.13      2826785.75     10228112.00
      2826705.69     10228403.09
#Sta/Elev= 30
  4908.6 1061.94  4915.7 1061.55  4922.3 1059.48  4930.0 1059.05  4936.6 1057.18
  4950.9 1054.63  4958.6 1052.42  4965.2 1049.25  4968.2 1046.72  4968.7 1046.22
  4977.2 1046.22  4977.7 1046.72  4979.5 1047.12  4993.8 1047.77  4997.0 1050.29
  5003.2 1050.29  5011.5 1051.84  5023.1 1053.29  5052.3 1054.77  5057.5 1055.82
  5084.1 1055.89  5097.1 1056.42  5125.6 1055.79  5146.4 1056.19  5171.1 1055.90
  5276.5 1058.31  5279.4 1058.41  5291.5 1058.65  5299.3 1060.74  5301.9 1060.74
#Mann=5,-1,0
  4908.6    0.12       0  4968.2    0.07       0  4977.7    0.12       0
  5276.5    0.05       0  5279.4    0.12       0
Bank Sta=4968.2,4977.7
Exp/Cntr=0.3,0.1

Chan Stop Cuts=-1