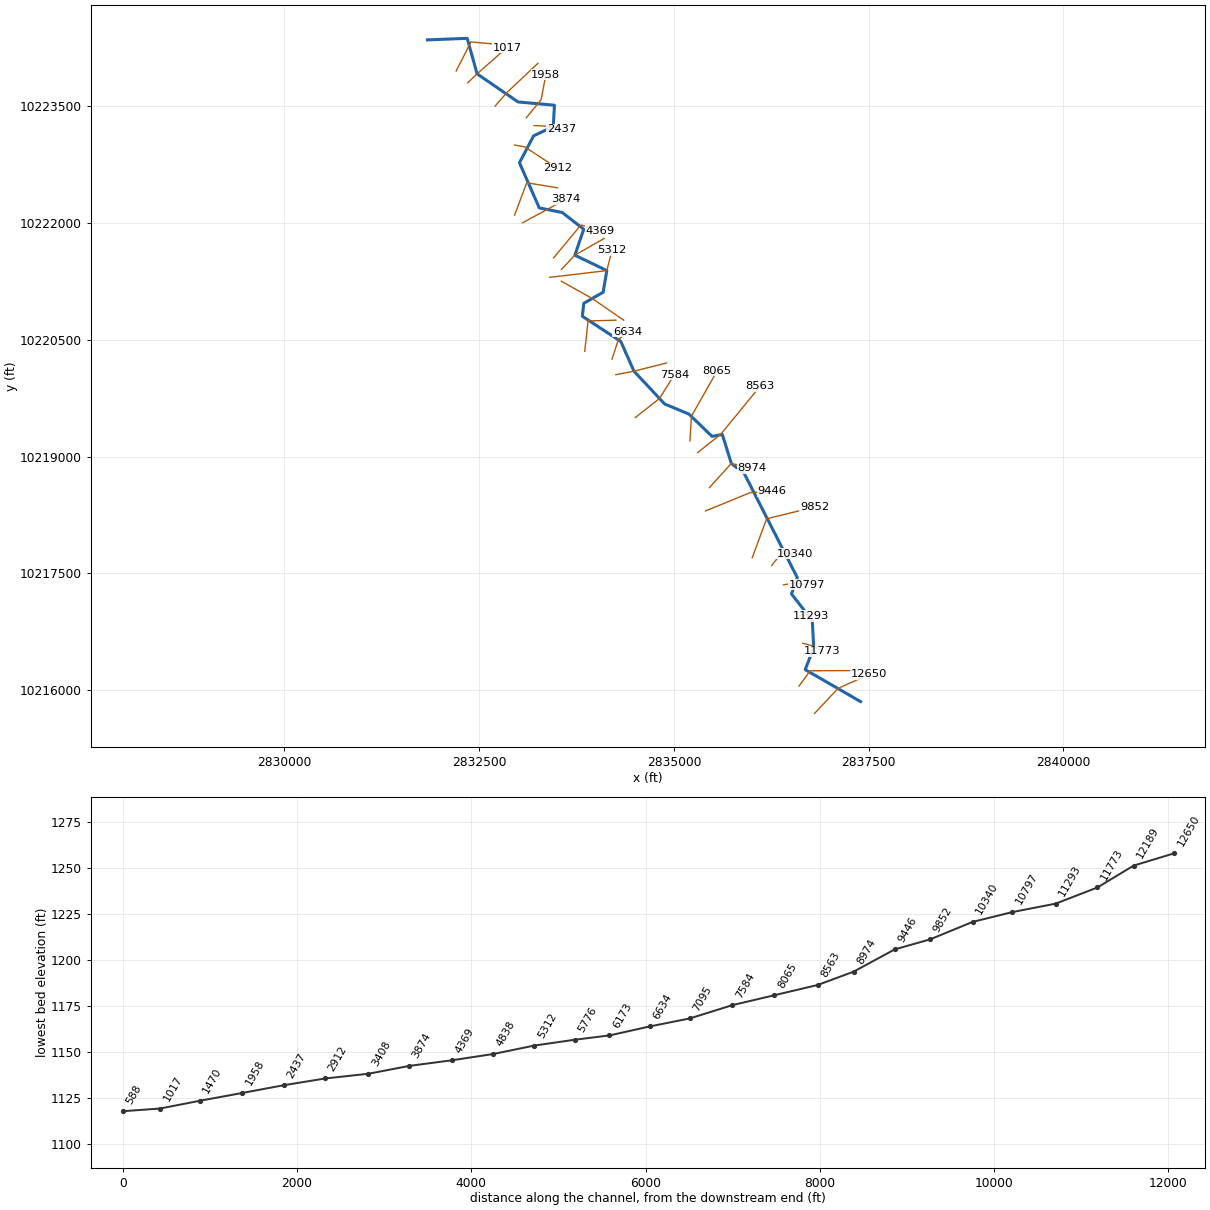
--- LITTLE LLANO 028.prj (project) ---

Proj Title=LITTLE LLANO 028 Base Level Engineering
Current Plan=p01
Default Exp/Contr=0.3,0.1
English Units
Geom File=g01
Flow File=f01
Plan File=p01
BEGIN DESCRIPTION:
LITTLE LLANO 028
END DESCRIPTION:

--- LITTLE LLANO 028.p01 (plan) ---

Plan Title=Multiple Run
Short Identifier=Multiple
Geom File=g01
Flow File=f01
Subcritical Flow
K Sum by GR= 0
Std Step Tol= 0.01
Critical Tol= 0.01
Num of Std Step Trials= 20
Max Error Tol= 0.3
Flow Tol Ratio= 0.001
Split Flow NTrial= 30
Split Flow Tol= 0.02
Split Flow Ratio= 0.02
Log Output Level= 0
Friction Slope Method= 1
Unsteady Friction Slope Method= 2
Unsteady Bridges Friction Slope Method= 1
Parabolic Critical Depth
Global Vel Dist=  1 , 1 , 1
Global Log Level= 0
CheckData=True
Encroach Param= -1, 0, 0, 0
BEGIN DESCRIPTION:
Multiple Run
END DESCRIPTION:

--- LITTLE LLANO 028.f01 (steady flow) ---

Flow Title=Multiple
Number of Profiles=7
Profile Names=10-year,25-year,50-year,1pct_min,100-year,1pct_plu,500-year
River Rch & RM= LITTLE LLANO 028,Reach-1,12650
      72     134     208     107     324     979     852
River Rch & RM= LITTLE LLANO 028,Reach-1,7095
     108     220     353     188     566    1710    1555
Boundary for River Rch & Prof#=LITTLE LLANO 028,Reach-1,1
Up Type=0
Dn Type=3
Dn Slope=0.005
Boundary for River Rch & Prof#=LITTLE LLANO 028,Reach-1,2
Up Type=0
Dn Type=3
Dn Slope=0.005
Boundary for River Rch & Prof#=LITTLE LLANO 028,Reach-1,3
Up Type=0
Dn Type=3
Dn Slope=0.005
Boundary for River Rch & Prof#=LITTLE LLANO 028,Reach-1,4
Up Type=0
Dn Type=3
Dn Slope=0.005
Boundary for River Rch & Prof#=LITTLE LLANO 028,Reach-1,5
Up Type=0
Dn Type=3
Dn Slope=0.005
Boundary for River Rch & Prof#=LITTLE LLANO 028,Reach-1,6
Up Type=0
Dn Type=3
Dn Slope=0.005
Boundary for River Rch & Prof#=LITTLE LLANO 028,Reach-1,7
Up Type=0
Dn Type=3
Dn Slope=0.005

--- LITTLE LLANO 028.g01 (geometry) ---

Geom Title=Existing Conditions

River Reach=LITTLE LLANO 028,Reach-1
Reach XY= 30
      2837396.00     10215854.00      2836685.25     10216265.00
      2836794.75     10216545.00      2836776.25     10216893.00
      2836509.75     10217237.00      2836584.25     10217446.00
      2835900.75     10218788.00      2835736.75     10218913.00
      2835621.75     10219285.00      2835489.00     10219261.00
      2835194.00     10219546.00      2834881.25     10219677.00
      2834487.25     10220098.00      2834319.00     10220479.00
      2833824.50     10220804.00      2833843.50     10220970.00
      2834091.50     10221112.00      2834139.25     10221390.00
      2833728.75     10221588.00      2833843.00     10221921.00
      2833566.50     10222136.00      2833272.25     10222195.00
      2833018.00     10222775.00      2833199.50     10223121.00
      2833452.00     10223240.00      2833466.75     10223514.00
      2832999.50     10223556.00      2832474.00     10223917.00
      2832347.00     10224373.00      2831837.00     10224353.00

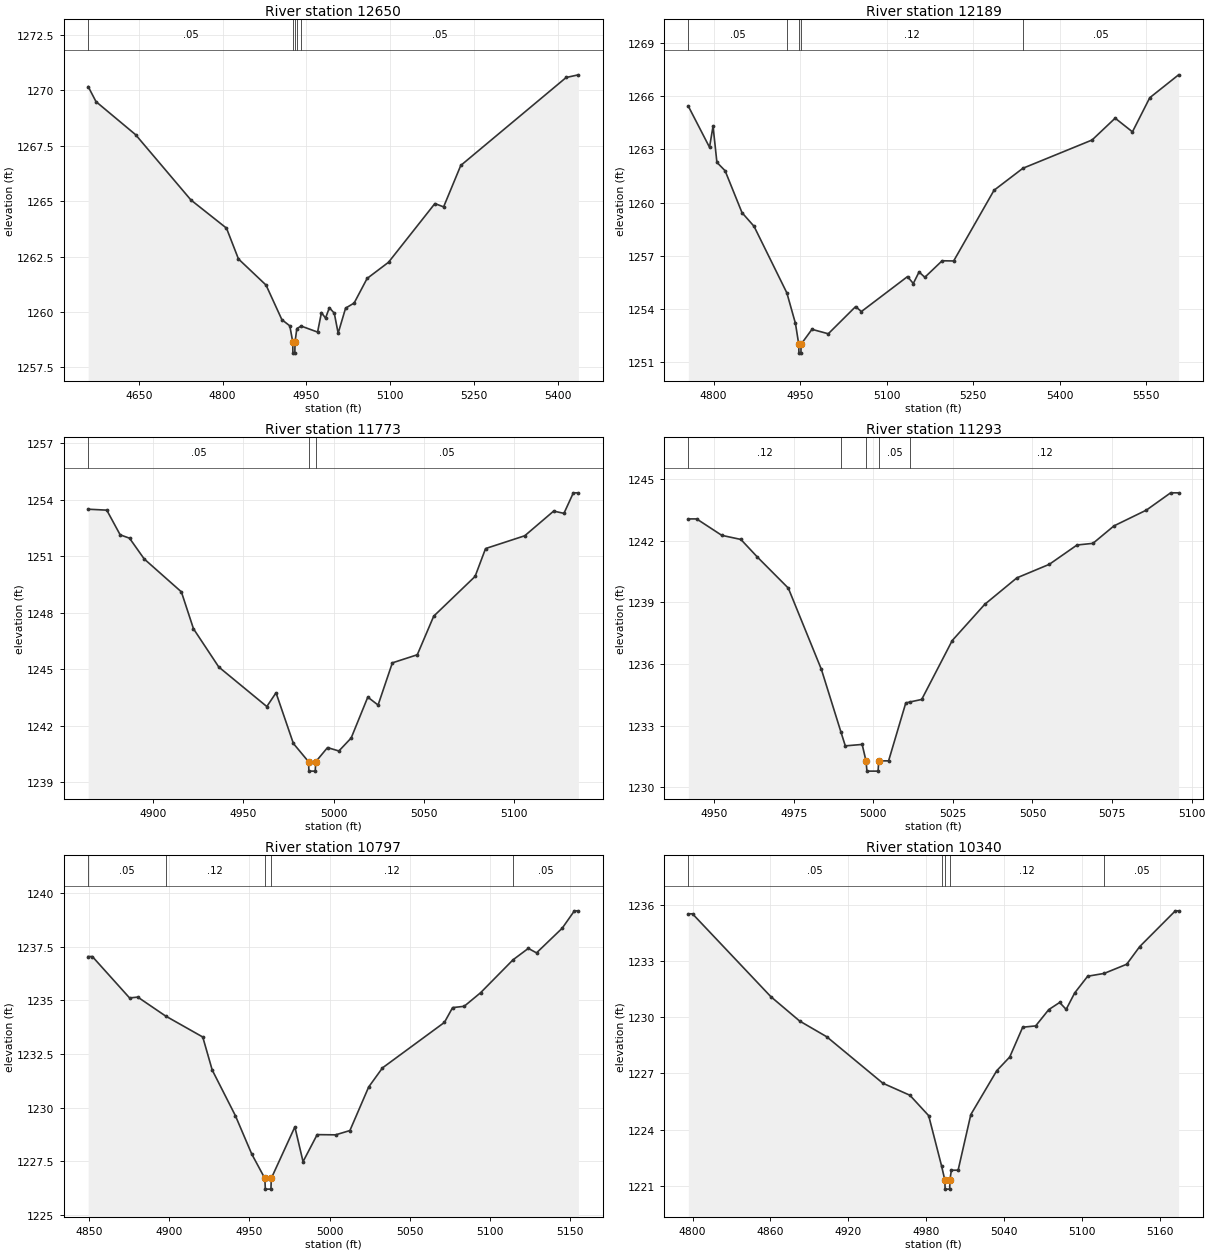
Type RM Length L Ch R = 1,12650,461,461,461
BEGIN DESCRIPTION:
LITTLE LLANO 028 27.0
END DESCRIPTION:
XS GIS Cut Line= 3
      2836805.65     10215703.08      2837107.25     10216024.00
      2837505.65     10216203.09
#Sta/Elev= 30
  4559.6 1270.17  4573.6 1269.49  4644.4 1268.00  4743.5 1265.05  4807.1 1263.78
  4828.5 1262.39  4877.9 1261.21  4906.2 1259.65  4920.4 1259.37  4925.7 1258.64
  4925.9 1258.14  4929.4 1258.14  4929.7 1258.64  4933.0 1259.25  4940.8 1259.36
  4970.1 1259.09  4977.0 1259.97  4984.3 1259.72  4991.2 1260.19  5000.0 1259.94
  5006.9 1259.04  5020.2 1260.17  5035.5 1260.40  5058.7 1261.51  5097.0 1262.24
  5180.0 1264.89  5195.6 1264.74  5226.3 1266.61  5414.9 1270.58  5436.8 1270.70
#Mann=5,-1,0
  4559.6    0.05       0  4925.7    0.05       0  4929.7    0.05       0
  4933.0    0.12       0  4940.8    0.05       0
Bank Sta=4925.7,4929.7
Exp/Cntr=0.3,0.1

Type RM Length L Ch R = 1,12189,416,416,416
BEGIN DESCRIPTION:
LITTLE LLANO 028 26.0
END DESCRIPTION:
XS GIS Cut Line= 3
      2836605.70     10216053.13      2836749.50     10216250.00
      2837355.69     10216253.11
#Sta/Elev= 30
  4756.2 1265.42  4792.9 1263.11  4799.0 1264.30  4805.7 1262.26  4819.9 1261.79
  4849.2 1259.43  4870.1 1258.66  4927.0 1254.91  4941.9 1253.19  4947.6 1252.02
  4947.9 1251.52  4951.4 1251.52  4951.6 1252.02  4970.5 1252.86  4998.8 1252.61
  5046.2 1254.14  5056.2 1253.86  5136.2 1255.83  5146.2 1255.44  5156.2 1256.09
  5166.2 1255.79  5196.2 1256.72  5216.2 1256.71  5286.2 1260.69  5336.3 1261.93
  5456.2 1263.52  5496.2 1264.75  5526.2 1263.98  5556.2 1265.90  5606.2 1267.19
#Mann=5,-1,0
  4756.2    0.05       0  4927.0    0.12       0  4947.6    0.07       0
  4951.6    0.12       0  5336.3    0.05       0
Bank Sta=4947.6,4951.6
Exp/Cntr=0.3,0.1

Type RM Length L Ch R = 1,11773,480,480,480
BEGIN DESCRIPTION:
LITTLE LLANO 028 25.0
END DESCRIPTION:
XS GIS Cut Line= 3
      2836655.70     10216603.11      2836787.25     10216569.00
      2836905.66     10216503.13
#Sta/Elev= 30
  4864.1 1253.50  4874.4 1253.45  4881.8 1252.14  4887.0 1251.96  4895.1 1250.86
  4915.7 1249.11  4922.4 1247.15  4936.4 1245.12  4963.0 1243.02  4968.1 1243.75
  4977.7 1241.06  4986.1 1240.09  4986.3 1239.59  4989.8 1239.59  4990.1 1240.09
  4996.6 1240.84  5002.9 1240.66  5009.7 1241.35  5018.9 1243.52  5024.6 1243.10
  5032.5 1245.34  5046.3 1245.77  5055.4 1247.82  5078.3 1249.93  5084.1 1251.41
  5105.8 1252.09  5121.8 1253.40  5127.5 1253.28  5132.7 1254.37  5135.5 1254.37
#Mann=3,-1,0
  4864.1    0.05       0  4986.1    0.05       0  4990.1    0.05       0
Bank Sta=4986.1,4990.1
Exp/Cntr=0.3,0.1

Type RM Length L Ch R = 1,11293,496,496,496
BEGIN DESCRIPTION:
LITTLE LLANO 028 24.0
END DESCRIPTION:
XS GIS Cut Line= 3
      2836605.66     10216953.10      2836661.25     10216970.00
      2836755.65     10216953.12
#Sta/Elev= 28
  4941.9 1243.06  4944.5 1243.06  4952.4 1242.26  4958.4 1242.06  4963.6 1241.20
  4973.3 1239.69  4983.7 1235.73  4989.8 1232.70  4991.2 1232.01  4996.5 1232.08
  4997.7 1231.28  4998.0 1230.78  5001.5 1230.78  5001.7 1231.28  5004.8 1231.28
  5010.2 1234.10  5011.6 1234.15  5015.2 1234.27  5024.8 1237.14  5035.0 1238.90
  5045.1 1240.19  5055.3 1240.85  5064.0 1241.79  5069.0 1241.87  5075.6 1242.72
  5085.8 1243.49  5093.4 1244.33  5095.9 1244.33
#Mann=5,-1,0
  4941.9    0.12       0  4989.8    0.05       0  4997.7    0.05       0
  5001.7    0.05       0  5011.6    0.12       0
Bank Sta=4997.7,5001.7
Exp/Cntr=0.3,0.1

Type RM Length L Ch R = 1,10797,457,457,457
BEGIN DESCRIPTION:
LITTLE LLANO 028 23.0
END DESCRIPTION:
XS GIS Cut Line= 3
      2836405.65     10217353.11      2836553.25     10217382.00
      2836705.64     10217353.12
#Sta/Elev= 30
  4849.6 1237.04  4852.2 1237.04  4875.4 1235.11  4880.5 1235.15  4897.8 1234.27
  4921.0 1233.29  4926.9 1231.75  4941.3 1229.63  4951.5 1227.84  4959.7 1226.70
  4960.0 1226.20  4963.5 1226.20  4963.7 1226.70  4978.4 1229.10  4983.5 1227.48
  4992.3 1228.74  5003.8 1228.73  5012.7 1228.93  5024.4 1230.96  5033.0 1231.85
  5071.6 1233.97  5076.7 1234.66  5083.9 1234.72  5094.1 1235.35  5114.4 1236.89
  5123.9 1237.42  5129.0 1237.21  5145.0 1238.36  5152.6 1239.17  5155.1 1239.17
#Mann=5,-1,0
  4849.6    0.05       0  4897.8    0.12       0  4959.7    0.07       0
  4963.7    0.12       0  5114.4    0.05       0
Bank Sta=4959.7,4963.7
Exp/Cntr=0.3,0.1

Type RM Length L Ch R = 1,10340,488,488,488
BEGIN DESCRIPTION:
LITTLE LLANO 028 22.0
END DESCRIPTION:
XS GIS Cut Line= 3
      2836255.68     10217603.11      2836381.25     10217763.00
      2836555.67     10217753.11
#Sta/Elev= 30
  4796.7 1235.52  4799.9 1235.52  4860.3 1231.10  4882.5 1229.80  4903.4 1228.96
  4946.7 1226.48  4967.5 1225.84  4982.0 1224.75  4991.9 1222.08  4994.4 1221.33
  4994.7 1220.83  4998.2 1220.83  4998.4 1221.33  4999.5 1221.84  5004.7 1221.84
  5014.5 1224.81  5034.5 1227.15  5044.5 1227.88  5054.5 1229.47  5064.5 1229.54
  5074.6 1230.41  5083.0 1230.79  5088.0 1230.42  5094.6 1231.30  5104.6 1232.19
  5117.3 1232.34  5134.7 1232.83  5144.7 1233.77  5172.2 1235.68  5174.7 1235.68
#Mann=5,-1,0
  4796.7    0.05       0  4991.9    0.12       0  4994.4    0.07       0
  4998.4    0.12       0  5117.3    0.05       0
Bank Sta=4994.4,4998.4
Exp/Cntr=0.3,0.1

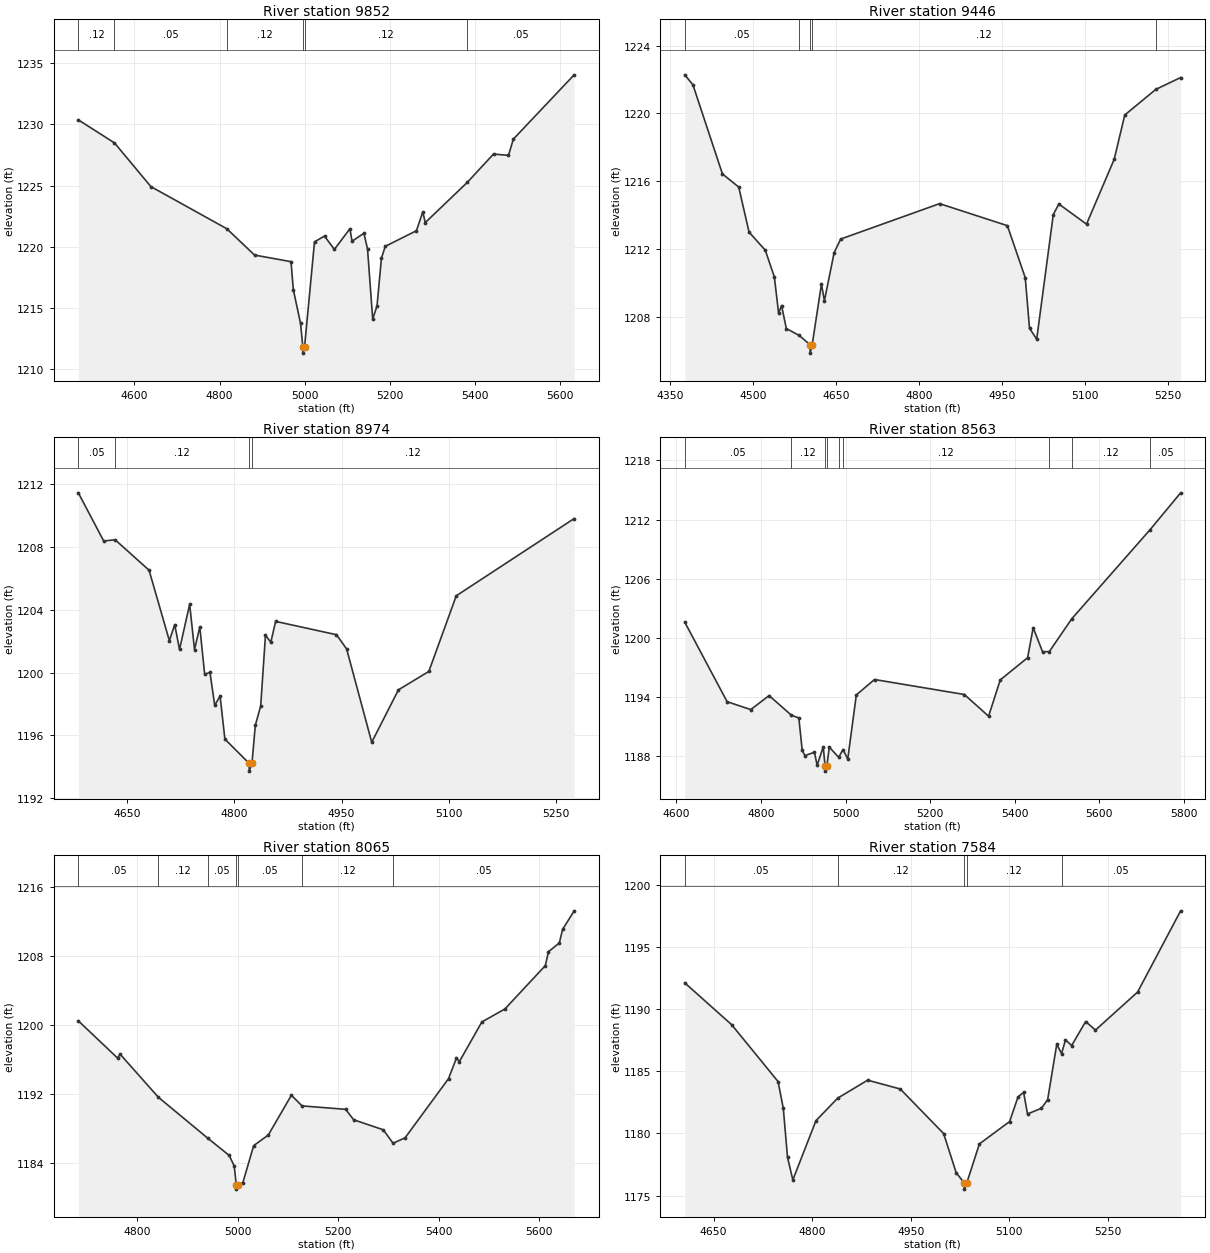
Type RM Length L Ch R = 1,9852,406,406,406
BEGIN DESCRIPTION:
LITTLE LLANO 028 21.0
END DESCRIPTION:
XS GIS Cut Line= 3
      2836005.70     10217703.14      2836190.25     10218202.00
      2836805.67     10218353.11
#Sta/Elev= 30
  4468.1 1230.37  4553.1 1228.49  4638.7 1224.92  4817.1 1221.48  4882.3 1219.33
  4968.1 1218.79  4973.5 1216.50  4990.5 1213.75  4995.9 1211.82  4996.2 1211.32
  4999.9 1211.82  5023.3 1220.41  5046.8 1220.88  5070.0 1219.79  5106.5 1221.48
  5111.6 1220.46  5139.5 1221.11  5148.0 1219.81  5160.1 1214.10  5170.3 1215.18
  5180.6 1219.06  5189.6 1220.04  5263.0 1221.32  5277.9 1222.86  5283.6 1221.98
  5382.6 1225.27  5444.1 1227.58  5479.3 1227.47  5490.8 1228.80  5633.7 1234.05
#Mann=6,-1,0
  4468.1    0.12       0  4553.1    0.05       0  4817.1    0.12       0
  4995.9    0.07       0  4999.9    0.12       0  5382.6    0.05       0
Bank Sta=4995.9,4999.9
Exp/Cntr=0.3,0.1

Type RM Length L Ch R = 1,9446,472,472,472
BEGIN DESCRIPTION:
LITTLE LLANO 028 20.0
END DESCRIPTION:
XS GIS Cut Line= 3
      2835405.70     10218303.12      2835982.75     10218539.00
      2836255.69     10218553.11
#Sta/Elev= 30
  4376.6 1222.28  4391.3 1221.69  4444.7 1216.43  4474.1 1215.66  4492.8 1213.00
  4522.2 1211.93  4538.6 1210.35  4546.2 1208.22  4551.6 1208.67  4560.2 1207.31
  4583.2 1206.91  4603.0 1206.36  4603.3 1205.86  4607.0 1206.36  4623.7 1209.93
  4629.1 1208.95  4646.7 1211.79  4658.5 1212.59  4837.4 1214.68  4960.0 1213.38
  4992.3 1210.31  5000.0 1207.33  5013.0 1206.68  5043.0 1214.03  5053.0 1214.66
  5103.1 1213.47  5153.1 1217.29  5172.3 1219.91  5228.4 1221.42  5273.3 1222.12
#Mann=5,-1,0
  4376.6    0.05       0  4583.2    0.12       0  4603.0    0.07       0
  4607.0    0.12       0  5228.4    0.05       0
Bank Sta=4603,4607
Exp/Cntr=0.3,0.1

Type RM Length L Ch R = 1,8974,411,411,411
BEGIN DESCRIPTION:
LITTLE LLANO 028 19.0
END DESCRIPTION:
XS GIS Cut Line= 3
      2835455.66     10218603.09      2835736.75     10218913.00
      2836005.66     10218853.12
#Sta/Elev= 30
  4581.6 1211.46  4617.1 1208.39  4633.1 1208.47  4680.6 1206.53  4709.0 1202.04
  4716.5 1203.06  4723.2 1201.48  4737.4 1204.36  4744.2 1201.47  4751.6 1202.92
  4758.4 1199.90  4765.8 1200.02  4772.5 1197.92  4780.0 1198.51  4786.7 1195.77
  4820.6 1194.23  4820.8 1193.73  4824.6 1194.23  4829.3 1196.65  4836.8 1197.88
  4843.5 1202.39  4851.0 1201.94  4857.7 1203.27  4942.9 1202.42  4957.1 1201.51
  4992.2 1195.57  5029.6 1198.91  5072.1 1200.08  5110.5 1204.90  5275.5 1209.82
#Mann=4,-1,0
  4581.6    0.05       0  4633.1    0.12       0  4820.6    0.07       0
  4824.6    0.12       0
Bank Sta=4820.6,4824.6
Exp/Cntr=0.3,0.1

Type RM Length L Ch R = 1,8563,498,498,498
BEGIN DESCRIPTION:
LITTLE LLANO 028 18.0
END DESCRIPTION:
XS GIS Cut Line= 3
      2835305.72     10219053.14      2835603.25     10219290.00
      2836105.70     10219903.12
#Sta/Elev= 30
  4619.7 1201.60  4719.8 1193.54  4775.8 1192.74  4819.1 1194.16  4871.9 1192.17
  4889.5 1191.89  4897.5 1188.60  4903.9 1188.08  4926.4 1188.41  4932.8 1187.09
  4947.2 1188.97  4951.6 1187.00  4951.8 1186.50  4955.6 1187.00  4961.6 1188.93
  4983.8 1187.90  4994.0 1188.69  5005.2 1187.72  5025.5 1194.23  5068.5 1195.79
  5281.0 1194.27  5338.4 1192.07  5366.0 1195.75  5430.7 1198.00  5443.9 1201.04
  5466.1 1198.60  5482.0 1198.62  5535.2 1201.95  5720.4 1210.98  5792.7 1214.72
#Mann=9,-1,0
  4619.7    0.05       0  4871.9    0.12       0  4951.6    0.07       0
  4955.6    0.12       0  4983.8    0.05       0  4994.0    0.12       0
  5482.0    0.05       0  5535.2    0.12       0  5720.4    0.05       0
Bank Sta=4951.6,4955.6
Exp/Cntr=0.3,0.1

Type RM Length L Ch R = 1,8065,481,481,481
BEGIN DESCRIPTION:
LITTLE LLANO 028 17.0
END DESCRIPTION:
XS GIS Cut Line= 3
      2835205.68     10219203.10      2835225.25     10219520.00
      2835555.67     10220103.09
#Sta/Elev= 30
  4682.5 1200.46  4760.6 1196.14  4765.7 1196.59  4841.8 1191.59  4940.5 1186.82
  4983.1 1184.82  4993.1 1183.59  4997.1 1181.41  4997.3 1180.91  5001.1 1181.41
  5010.2 1181.66  5031.8 1185.96  5061.0 1187.20  5106.9 1191.82  5128.1 1190.58
  5215.0 1190.18  5230.9 1188.97  5290.1 1187.80  5309.4 1186.24  5333.4 1186.87
  5419.9 1193.74  5435.8 1196.15  5441.5 1195.72  5486.3 1200.33  5532.3 1201.84
  5612.8 1206.88  5619.0 1208.49  5640.6 1209.50  5647.2 1211.08  5670.2 1213.24
#Mann=7,-1,0
  4682.5    0.05       0  4841.8    0.12       0  4940.5    0.05       0
  4997.1    0.05       0  5001.1    0.05       0  5128.1    0.12       0
  5309.4    0.05       0
Bank Sta=4997.1,5001.1
Exp/Cntr=0.3,0.1

Type RM Length L Ch R = 1,7584,489,489,489
BEGIN DESCRIPTION:
LITTLE LLANO 028 16.0
END DESCRIPTION:
XS GIS Cut Line= 3
      2834505.68     10219503.11      2834815.00     10219747.00
      2835005.66     10220053.07
#Sta/Elev= 30
  4606.1 1192.12  4677.5 1188.75  4748.0 1184.18  4756.0 1182.02  4762.4 1178.08
  4770.5 1176.26  4805.7 1181.03  4838.7 1182.84  4884.3 1184.29  4934.0 1183.58
  5000.0 1179.99  5019.0 1176.85  5031.2 1176.02  5031.4 1175.52  5035.2 1176.02
  5054.4 1179.16  5100.4 1180.96  5113.2 1182.95  5121.7 1183.30  5127.6 1181.57
  5148.8 1182.03  5158.3 1182.73  5172.1 1187.18  5179.4 1186.43  5185.4 1187.53
  5194.8 1187.08  5216.1 1189.01  5231.0 1188.32  5295.1 1191.38  5360.6 1197.92
#Mann=5,-1,0
  4606.1    0.05       0  4838.7    0.12       0  5031.2    0.07       0
  5035.2    0.12       0  5179.4    0.05       0
Bank Sta=5031.2,5035.2
Exp/Cntr=0.3,0.1

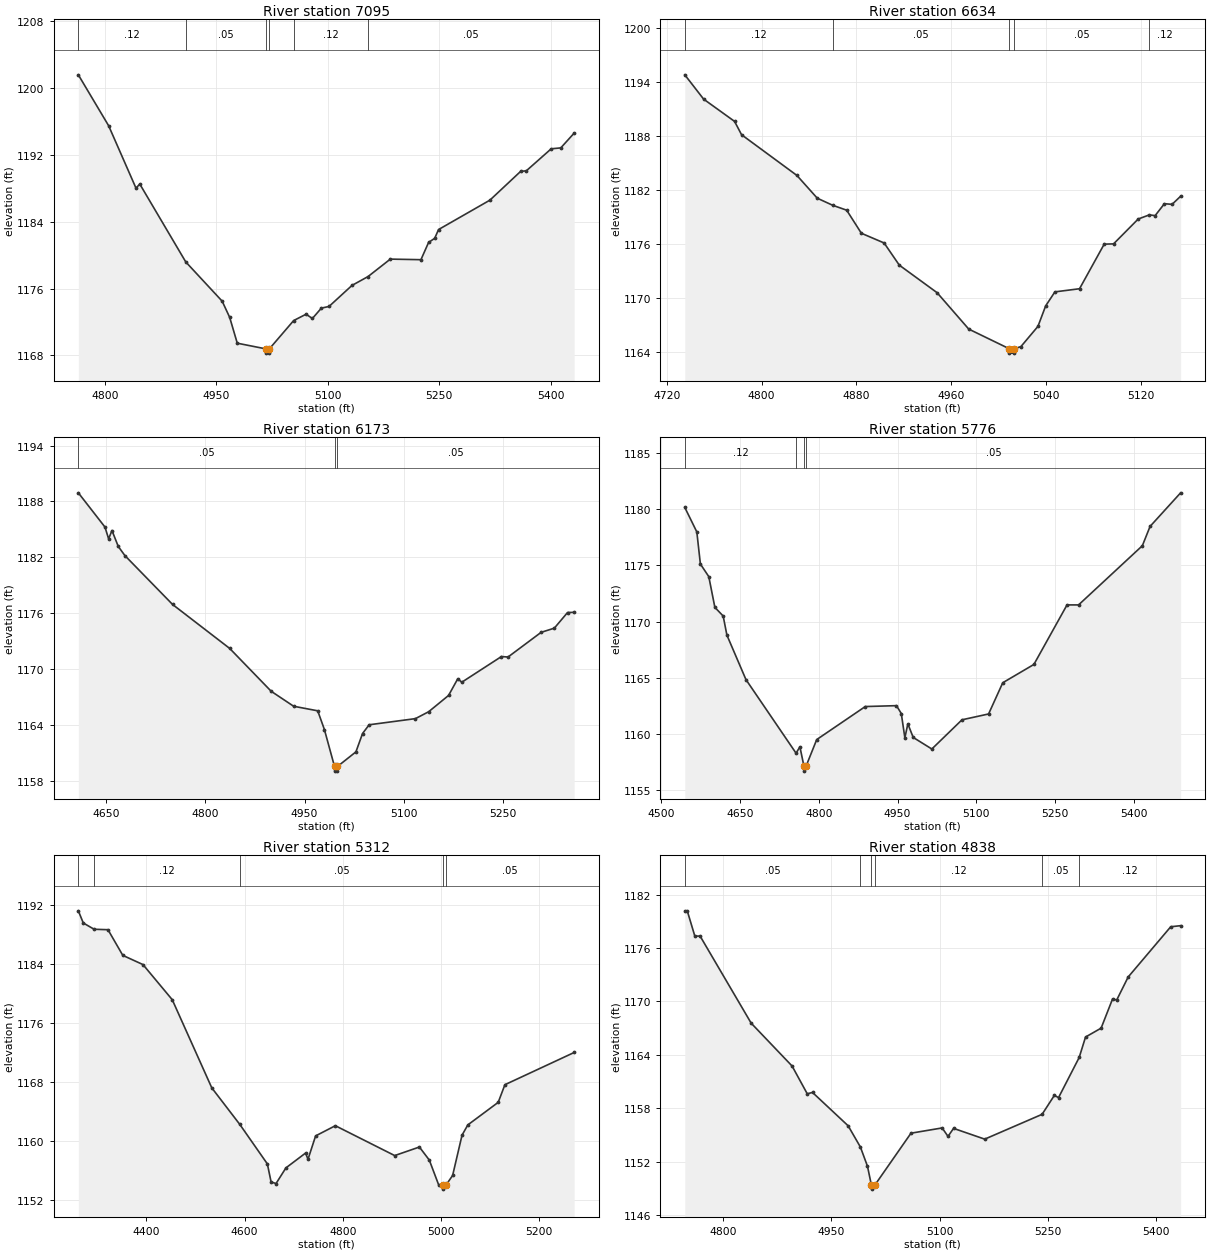
Type RM Length L Ch R = 1,7095,461,461,461
BEGIN DESCRIPTION:
LITTLE LLANO 028 15.0
END DESCRIPTION:
XS GIS Cut Line= 3
      2834255.66     10220053.11      2834487.25     10220098.00
      2834905.65     10220203.10
#Sta/Elev= 30
  4764.1 1201.61  4804.9 1195.51  4841.7 1188.04  4846.8 1188.53  4908.7 1179.20
  4957.7 1174.50  4967.8 1172.56  4978.0 1169.47  5017.0 1168.78  5017.2 1168.28
  5020.8 1168.28  5021.1 1168.78  5053.9 1172.18  5070.6 1172.94  5079.1 1172.43
  5091.2 1173.67  5101.5 1173.87  5132.4 1176.39  5154.0 1177.45  5184.0 1179.54
  5225.2 1179.47  5235.5 1181.54  5243.7 1182.03  5248.9 1183.08  5318.0 1186.60
  5359.3 1190.04  5367.1 1190.12  5400.5 1192.75  5413.4 1192.86  5431.4 1194.63
#Mann=6,-1,0
  4764.1    0.12       0  4908.7    0.05       0  5017.0    0.05       0
  5021.1    0.05       0  5053.9    0.12       0  5154.0    0.05       0
Bank Sta=5017,5021.1
Exp/Cntr=0.3,0.1

Type RM Length L Ch R = 1,6634,461,461,461
BEGIN DESCRIPTION:
LITTLE LLANO 028 14.0
END DESCRIPTION:
XS GIS Cut Line= 3
      2834205.70     10220253.15      2834287.50     10220505.00
      2834405.68     10220603.11
#Sta/Elev= 30
  4735.2 1194.81  4751.1 1192.11  4777.2 1189.64  4783.1 1188.16  4829.8 1183.64
  4847.0 1181.11  4860.1 1180.32  4871.8 1179.78  4884.2 1177.22  4903.4 1176.14
  4916.2 1173.68  4948.1 1170.62  4974.8 1166.58  5008.8 1164.41  5009.1 1163.91
  5013.0 1163.91  5013.3 1164.41  5018.8 1164.63  5033.2 1166.88  5039.7 1169.15
  5047.5 1170.71  5068.3 1171.06  5089.1 1176.01  5097.0 1176.04  5117.8 1178.80
  5127.2 1179.26  5132.1 1179.18  5139.9 1180.50  5146.4 1180.43  5153.6 1181.33
#Mann=5,-1,0
  4735.2    0.12       0  4860.1    0.05       0  5008.8    0.05       0
  5013.3    0.05       0  5127.2    0.12       0
Bank Sta=5008.8,5013.3
Exp/Cntr=0.3,0.1

Type RM Length L Ch R = 1,6173,397,397,397
BEGIN DESCRIPTION:
LITTLE LLANO 028 13.0
END DESCRIPTION:
XS GIS Cut Line= 3
      2833855.68     10220353.09      2833898.00     10220743.00
      2834255.66     10220753.11
#Sta/Elev= 30
  4607.8 1188.92  4648.1 1185.24  4653.6 1183.98  4658.7 1184.87  4668.2 1183.16
  4678.2 1182.18  4750.3 1176.93  4836.8 1172.20  4899.5 1167.60  4933.5 1165.99
  4969.9 1165.50  4980.0 1163.49  4995.3 1159.52  4995.6 1159.02  4999.5 1159.02
  4999.8 1159.52  5027.7 1161.09  5037.7 1163.06  5047.7 1164.00  5117.7 1164.66
  5137.7 1165.40  5167.8 1167.15  5181.8 1168.95  5187.8 1168.57  5247.8 1171.33
  5257.8 1171.28  5307.8 1173.93  5327.8 1174.38  5347.8 1176.06  5357.8 1176.08
#Mann=3,-1,0
  4607.8    0.05       0  4995.3    0.05       0  4999.8    0.05       0
Bank Sta=4995.3,4999.8
Exp/Cntr=0.3,0.1

Type RM Length L Ch R = 1,5776,464,464,464
BEGIN DESCRIPTION:
LITTLE LLANO 028 12.0
END DESCRIPTION:
XS GIS Cut Line= 3
      2833555.67     10221253.12      2833953.00     10221031.00
      2834355.72     10220753.09
#Sta/Elev= 30
  4544.8 1180.17  4567.7 1177.99  4574.5 1175.13  4590.5 1174.01  4602.1 1171.27
  4617.9 1170.50  4625.0 1168.80  4661.3 1164.84  4756.7 1158.29  4764.1 1158.85
  4771.5 1157.19  4771.9 1156.69  4776.3 1157.19  4796.1 1159.50  4888.6 1162.44
  4948.0 1162.52  4957.2 1161.82  4964.0 1159.66  4969.7 1160.90  4979.9 1159.69
  5015.4 1158.66  5072.8 1161.26  5123.5 1161.78  5150.5 1164.56  5209.8 1166.19
  5272.9 1171.49  5294.9 1171.49  5416.4 1176.76  5431.1 1178.48  5489.3 1181.47
#Mann=4,-1,0
  4544.8    0.12       0  4756.7    0.05       0  4771.5    0.03       0
  4776.3    0.05       0
Bank Sta=4771.5,4776.3
Exp/Cntr=0.3,0.1

Type RM Length L Ch R = 1,5312,474,474,474
BEGIN DESCRIPTION:
LITTLE LLANO 028 11.0
END DESCRIPTION:
XS GIS Cut Line= 3
      2833405.68     10221303.11      2834139.25     10221390.00
      2834205.69     10221653.14
#Sta/Elev= 30
  4261.3 1191.25  4271.4 1189.60  4293.5 1188.75  4321.7 1188.69  4351.9 1185.21
  4393.0 1183.96  4452.6 1179.20  4533.2 1167.24  4590.3 1162.28  4646.4 1156.93
  4654.0 1154.48  4664.1 1154.27  4684.2 1156.39  4724.2 1158.40  4729.2 1157.56
  4744.7 1160.73  4784.9 1162.11  4905.8 1158.06  4956.1 1159.22  4976.3 1157.45
  4995.7 1154.03  5004.5 1154.01  5004.9 1153.51  5009.8 1154.01  5023.8 1155.36
  5043.0 1160.83  5054.8 1162.22  5116.7 1165.28  5130.3 1167.67  5271.4 1172.04
#Mann=5,-1,0
  4261.3    0.05       0  4293.5    0.12       0  4590.3    0.05       0
  5004.5    0.05       0  5009.8    0.05       0
Bank Sta=5004.5,5009.8
Exp/Cntr=0.3,0.1

Type RM Length L Ch R = 1,4838,469,469,469
BEGIN DESCRIPTION:
LITTLE LLANO 028 10.0
END DESCRIPTION:
XS GIS Cut Line= 3
      2833555.72     10221403.15      2833728.75     10221588.00
      2834105.69     10221803.11
#Sta/Elev= 30
  4746.8 1180.19  4750.2 1180.19  4760.7 1177.35  4768.0 1177.35  4838.8 1167.56
  4895.5 1162.74  4916.5 1159.62  4923.8 1159.77  4973.2 1156.02  4990.2 1153.63
  5000.0 1151.47  5005.3 1149.40  5005.7 1148.90  5010.6 1149.40  5060.3 1155.19
  5103.5 1155.78  5111.6 1154.83  5119.3 1155.73  5162.5 1154.52  5242.0 1157.31
  5259.0 1159.44  5264.8 1159.19  5293.4 1163.70  5302.2 1166.00  5323.8 1167.00
  5339.7 1170.29  5345.4 1170.16  5361.3 1172.75  5420.3 1178.40  5434.0 1178.52
#Mann=6,-1,0
  4746.8    0.05       0  4990.2    0.12       0  5005.3    0.07       0
  5010.6    0.12       0  5242.0    0.05       0  5293.4    0.12       0
Bank Sta=5005.3,5010.6
Exp/Cntr=0.3,0.1

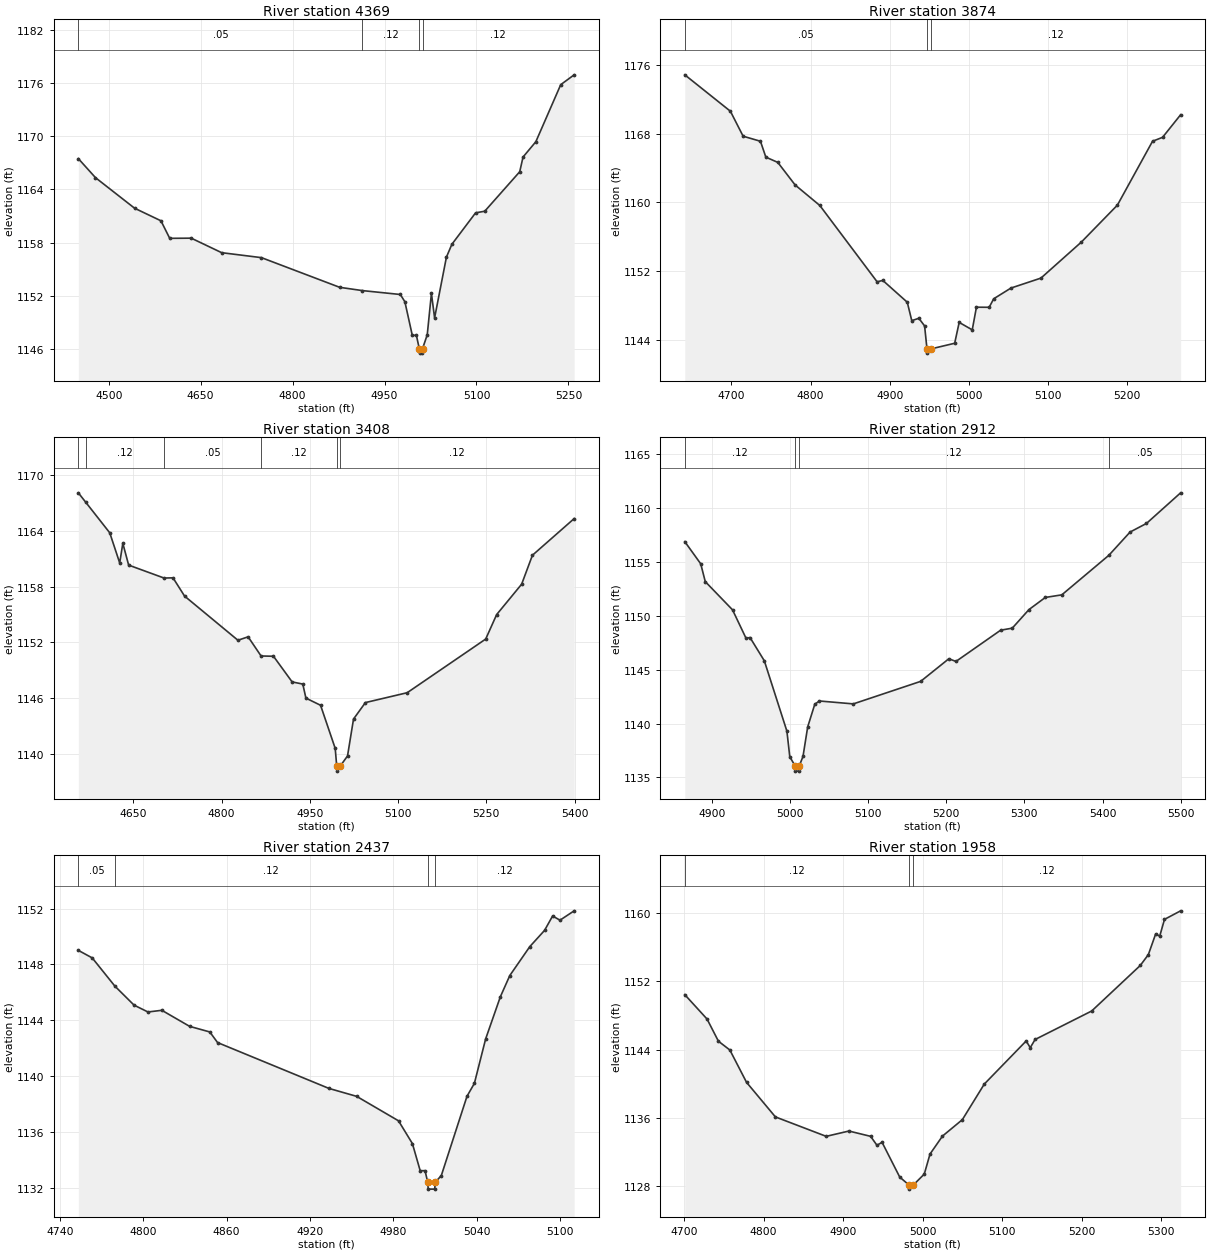
Type RM Length L Ch R = 1,4369,495,495,495
BEGIN DESCRIPTION:
LITTLE LLANO 028 9.0
END DESCRIPTION:
XS GIS Cut Line= 3
      2833455.70     10221553.13      2833806.75     10221976.00
      2834055.70     10221903.11
#Sta/Elev= 30
  4450.4 1167.48  4478.4 1165.33  4542.2 1161.88  4585.2 1160.46  4599.5 1158.48
  4634.6 1158.50  4684.3 1156.86  4749.2 1156.30  4876.8 1152.95  4913.9 1152.58
  4975.8 1152.14  4983.2 1151.32  4995.3 1147.53  5002.0 1147.53  5006.7 1146.02
  5007.1 1145.52  5011.6 1145.52  5012.0 1146.02  5019.7 1147.59  5026.5 1152.26
  5031.7 1149.50  5051.0 1156.36  5059.9 1157.81  5098.6 1161.36  5113.5 1161.54
  5170.6 1166.00  5176.0 1167.66  5196.9 1169.39  5237.5 1175.83  5259.4 1176.94
#Mann=4,-1,0
  4450.4    0.05       0  4913.9    0.12       0  5006.7    0.07       0
  5012.0    0.12       0
Bank Sta=5006.7,5012
Exp/Cntr=0.3,0.1

Type RM Length L Ch R = 1,3874,466,466,466
BEGIN DESCRIPTION:
LITTLE LLANO 028 8.0
END DESCRIPTION:
XS GIS Cut Line= 3
      2833055.65     10222003.10      2833371.25     10222174.00
      2833605.65     10222303.09
#Sta/Elev= 30
  4641.1 1174.84  4698.7 1170.60  4714.8 1167.69  4736.7 1167.10  4743.5 1165.25
  4758.6 1164.64  4780.5 1162.01  4811.7 1159.62  4884.1 1150.73  4891.3 1150.89
  4922.2 1148.35  4927.9 1146.20  4936.8 1146.48  4944.1 1145.59  4947.1 1142.92
  4947.5 1142.42  4952.5 1142.92  4982.1 1143.57  4987.8 1146.00  5004.3 1145.13
  5009.6 1147.77  5025.7 1147.76  5031.4 1148.75  5053.2 1150.00  5091.1 1151.16
  5142.1 1155.35  5187.7 1159.66  5232.1 1167.10  5244.8 1167.56  5267.6 1170.19
#Mann=3,-1,0
  4641.1    0.05       0  4947.1    0.07       0  4952.5    0.12       0
Bank Sta=4947.1,4952.5
Exp/Cntr=0.3,0.1

Type RM Length L Ch R = 1,3408,496,496,496
BEGIN DESCRIPTION:
LITTLE LLANO 028 7.0
END DESCRIPTION:
XS GIS Cut Line= 3
      2832955.67     10222103.08      2833111.75     10222518.00
      2833505.64     10222453.12
#Sta/Elev= 30
  4556.7 1168.08  4569.5 1167.05  4610.1 1163.78  4627.0 1160.54  4632.3 1162.65
  4642.2 1160.31  4702.3 1158.92  4717.6 1158.94  4737.2 1156.98  4827.9 1152.23
  4845.2 1152.60  4867.2 1150.54  4888.3 1150.51  4920.0 1147.75  4938.1 1147.52
  4943.4 1146.01  4968.3 1145.24  4993.2 1140.60  4995.8 1138.66  4996.2 1138.16
  5001.2 1138.66  5014.1 1139.79  5024.3 1143.76  5044.5 1145.53  5115.5 1146.59
  5248.9 1152.36  5267.5 1154.99  5310.0 1158.26  5328.3 1161.37  5399.2 1165.31
#Mann=6,-1,0
  4556.7    0.05       0  4569.5    0.12       0  4702.3    0.05       0
  4867.2    0.12       0  4995.8    0.07       0  5001.2    0.12       0
Bank Sta=4995.8,5001.2
Exp/Cntr=0.3,0.1

Type RM Length L Ch R = 1,2912,475,475,475
BEGIN DESCRIPTION:
LITTLE LLANO 028 6.0
END DESCRIPTION:
XS GIS Cut Line= 3
      2832955.66     10223003.12      2833088.00     10222978.00
      2833505.66     10222703.12
#Sta/Elev= 30
  4865.3 1156.89  4885.7 1154.83  4891.5 1153.18  4926.4 1150.56  4943.7 1147.92
  4948.8 1147.99  4967.1 1145.83  4996.0 1139.30  4999.7 1136.92  5006.4 1136.09
  5006.9 1135.59  5011.5 1135.59  5011.9 1136.09  5016.6 1136.95  5022.6 1139.69
  5031.7 1141.80  5037.7 1142.10  5081.0 1141.83  5167.2 1143.92  5203.3 1146.02
  5212.4 1145.77  5269.6 1148.67  5284.5 1148.86  5305.8 1150.58  5326.8 1151.71
  5347.9 1151.95  5408.1 1155.62  5435.3 1157.78  5456.3 1158.58  5500.0 1161.42
#Mann=4,-1,0
  4865.3    0.12       0  5006.4    0.07       0  5011.9    0.12       0
  5408.1    0.05       0
Bank Sta=5006.4,5011.9
Exp/Cntr=0.3,0.1

Type RM Length L Ch R = 1,2437,479,479,479
BEGIN DESCRIPTION:
LITTLE LLANO 028 5.0
END DESCRIPTION:
XS GIS Cut Line= 3
      2833205.65     10223253.11      2833452.00     10223240.00
      2833555.73     10223203.10
#Sta/Elev= 30
  4753.3 1149.01  4763.3 1148.47  4779.6 1146.45  4793.4 1145.09  4803.4 1144.60
  4813.4 1144.72  4833.4 1143.57  4847.9 1143.17  4853.5 1142.41  4933.6 1139.13
  4953.6 1138.56  4983.7 1136.81  4993.7 1135.18  4999.3 1133.24  5002.8 1133.24
  5004.7 1132.42  5005.1 1131.92  5009.7 1131.92  5010.2 1132.42  5014.5 1132.89
  5033.0 1138.57  5038.3 1139.49  5046.4 1142.67  5057.0 1145.69  5063.8 1147.21
  5078.2 1149.28  5088.8 1150.44  5094.6 1151.47  5099.9 1151.17  5110.1 1151.84
#Mann=4,-1,0
  4753.3    0.05       0  4779.6    0.12       0  5004.7    0.07       0
  5010.2    0.12       0
Bank Sta=5004.7,5010.2
Exp/Cntr=0.3,0.1

Type RM Length L Ch R = 1,1958,488,488,488
BEGIN DESCRIPTION:
LITTLE LLANO 028 4.0
END DESCRIPTION:
XS GIS Cut Line= 3
      2833105.69     10223353.12      2833296.00     10223584.00
      2833355.68     10223903.07
#Sta/Elev= 30
  4700.8 1150.41  4728.8 1147.56  4743.1 1144.97  4757.5 1143.94  4778.5 1140.16
  4814.8 1136.12  4878.7 1133.85  4907.3 1134.47  4934.6 1133.85  4942.5 1132.81
  4949.0 1133.15  4971.2 1129.09  4982.6 1128.18  4983.1 1127.68  4988.5 1128.18
  5002.1 1129.44  5009.3 1131.78  5025.0 1133.88  5050.0 1135.80  5077.6 1139.96
  5130.3 1145.00  5135.4 1144.21  5141.5 1145.17  5212.7 1148.50  5273.8 1153.82
  5284.0 1155.09  5293.2 1157.51  5298.3 1157.25  5304.3 1159.21  5324.6 1160.21
#Mann=3,-1,0
  4700.8    0.12       0  4982.6    0.07       0  4988.5    0.12       0
Bank Sta=4982.6,4988.5
Exp/Cntr=0.3,0.1

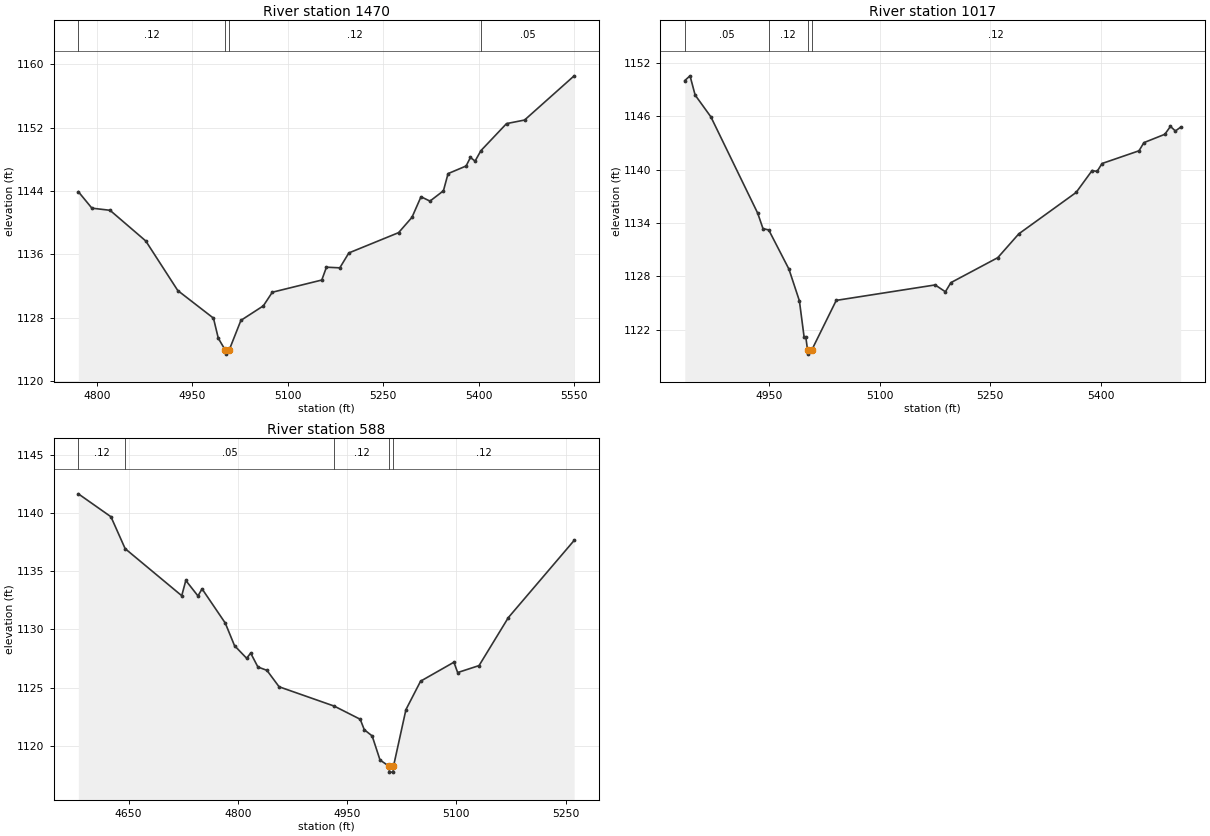
Type RM Length L Ch R = 1,1470,453,453,453
BEGIN DESCRIPTION:
LITTLE LLANO 028 3.0
END DESCRIPTION:
XS GIS Cut Line= 3
      2832705.71     10223503.14      2832855.75     10223676.00
      2833255.69     10224053.12
#Sta/Elev= 30
  4771.1 1143.92  4792.4 1141.84  4820.9 1141.57  4877.0 1137.70  4927.3 1131.44
  4983.3 1127.96  4990.9 1125.42  5001.9 1123.92  5002.4 1123.42  5007.9 1123.92
  5026.4 1127.68  5061.6 1129.51  5075.7 1131.23  5153.4 1132.77  5160.7 1134.39
  5181.7 1134.31  5195.9 1136.19  5274.0 1138.75  5295.0 1140.68  5309.2 1143.28
  5323.3 1142.73  5344.4 1144.03  5351.7 1146.20  5380.0 1147.16  5386.8 1148.24
  5394.1 1147.78  5403.3 1149.10  5443.5 1152.51  5471.8 1152.96  5549.7 1158.54
#Mann=4,-1,0
  4771.1    0.12       0  5001.9    0.07       0  5007.9    0.12       0
  5403.3    0.05       0
Bank Sta=5001.9,5007.9
Exp/Cntr=0.3,0.1

Type RM Length L Ch R = 1,1017,429,429,429
BEGIN DESCRIPTION:
LITTLE LLANO 028 2.0
END DESCRIPTION:
XS GIS Cut Line= 3
      2832355.70     10223803.13      2832474.00     10223917.00
      2832855.70     10224253.12
#Sta/Elev= 30
  4835.8 1150.03  4842.9 1150.56  4849.8 1148.40  4871.2 1145.94  4934.7 1135.10
  4941.9 1133.36  4949.7 1133.21  4977.1 1128.80  4991.3 1125.23  4997.7 1121.15
  5000.0 1121.15  5002.3 1119.73  5002.8 1119.23  5008.3 1119.73  5041.3 1125.28
  5175.5 1127.02  5189.4 1126.25  5196.9 1127.28  5260.5 1130.09  5289.0 1132.77
  5366.8 1137.43  5388.5 1139.90  5395.2 1139.79  5402.0 1140.69  5452.1 1142.12
  5458.8 1143.04  5487.2 1143.98  5494.8 1144.87  5501.5 1144.35  5508.6 1144.78
#Mann=4,-1,0
  4835.8    0.05       0  4949.7    0.12       0  5002.3    0.07       0
  5008.3    0.12       0
Bank Sta=5002.3,5008.3
Exp/Cntr=0.3,0.1

Type RM Length L Ch R = 1,588,0,0,0
BEGIN DESCRIPTION:
LITTLE LLANO 028 1.0
END DESCRIPTION:
XS GIS Cut Line= 3
      2832205.68     10223953.10      2832395.00     10224327.00
      2832655.71     10224303.11
#Sta/Elev= 30
  4580.9 1141.65  4625.7 1139.68  4645.2 1136.94  4722.9 1132.90  4728.5 1134.21
  4745.2 1132.88  4750.8 1133.49  4782.7 1130.55  4795.4 1128.61  4812.0 1127.53
  4817.6 1127.97  4827.5 1126.78  4839.9 1126.49  4856.6 1125.08  4932.3 1123.42
  4968.0 1122.29  4973.6 1121.39  4984.4 1120.86  4995.2 1118.79  5007.7 1118.25
  5008.2 1117.75  5013.2 1117.75  5013.7 1118.25  5030.8 1123.12  5050.9 1125.56
  5096.7 1127.19  5101.8 1126.30  5131.2 1126.90  5171.4 1131.02  5261.8 1137.65
#Mann=5,-1,0
  4580.9    0.12       0  4645.2    0.05       0  4932.3    0.12       0
  5007.7    0.07       0  5013.7    0.12       0
Bank Sta=5007.7,5013.7
Exp/Cntr=0.3,0.1

Chan Stop Cuts=-1