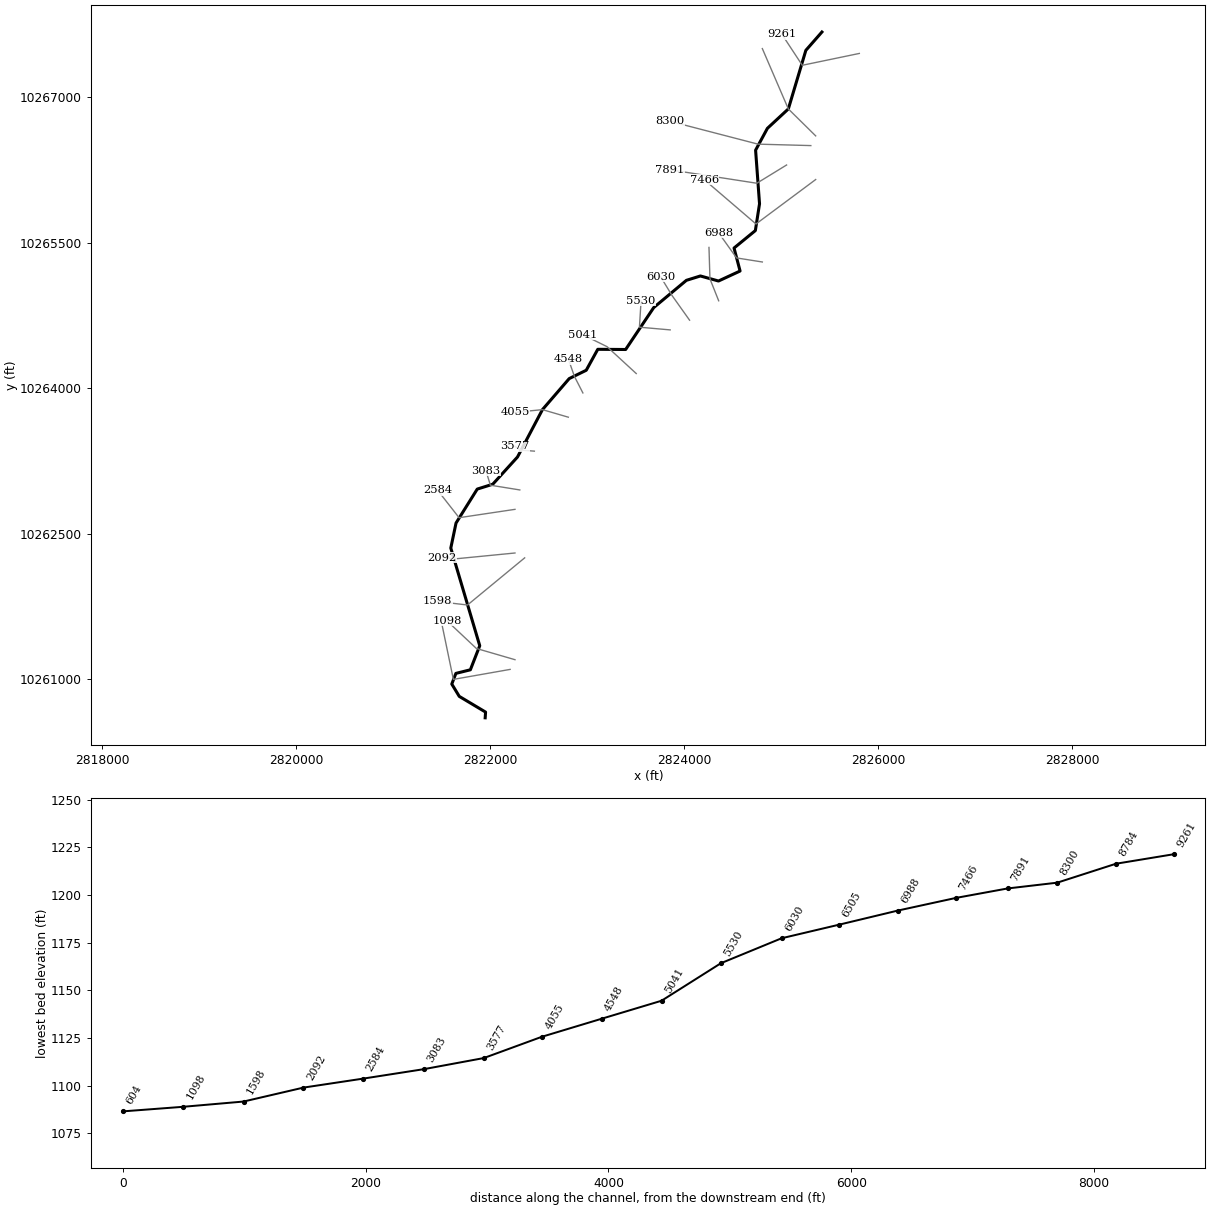
--- LITTLE LLANO 031.prj (project) ---

Proj Title=LITTLE LLANO 031 Base Level Engineering
Current Plan=p01
Default Exp/Contr=0.3,0.1
English Units
Geom File=g01
Flow File=f01
Plan File=p01
BEGIN DESCRIPTION:
LITTLE LLANO 031
END DESCRIPTION:

--- LITTLE LLANO 031.p01 (plan) ---

Plan Title=Multiple Run
Short Identifier=Multiple
Geom File=g01
Flow File=f01
Subcritical Flow
K Sum by GR= 0
Std Step Tol= 0.01
Critical Tol= 0.01
Num of Std Step Trials= 20
Max Error Tol= 0.3
Flow Tol Ratio= 0.001
Split Flow NTrial= 30
Split Flow Tol= 0.02
Split Flow Ratio= 0.02
Log Output Level= 0
Friction Slope Method= 1
Unsteady Friction Slope Method= 2
Unsteady Bridges Friction Slope Method= 1
Parabolic Critical Depth
Global Vel Dist=  1 , 1 , 1
Global Log Level= 0
CheckData=True
Encroach Param= -1, 0, 0, 0
BEGIN DESCRIPTION:
Multiple Run
END DESCRIPTION:

--- LITTLE LLANO 031.f01 (steady flow) ---

Flow Title=Multiple
Number of Profiles=7
Profile Names=10-year,25-year,50-year,1pct_min,100-year,1pct_plu,500-year
River Rch & RM= LITTLE LLANO 031,Reach-1,9261
      60     111     172      88     266     804     690
Boundary for River Rch & Prof#=LITTLE LLANO 031,Reach-1,1
Up Type=0
Dn Type=3
Dn Slope=0.005
Boundary for River Rch & Prof#=LITTLE LLANO 031,Reach-1,2
Up Type=0
Dn Type=3
Dn Slope=0.005
Boundary for River Rch & Prof#=LITTLE LLANO 031,Reach-1,3
Up Type=0
Dn Type=3
Dn Slope=0.005
Boundary for River Rch & Prof#=LITTLE LLANO 031,Reach-1,4
Up Type=0
Dn Type=3
Dn Slope=0.005
Boundary for River Rch & Prof#=LITTLE LLANO 031,Reach-1,5
Up Type=0
Dn Type=3
Dn Slope=0.005
Boundary for River Rch & Prof#=LITTLE LLANO 031,Reach-1,6
Up Type=0
Dn Type=3
Dn Slope=0.005
Boundary for River Rch & Prof#=LITTLE LLANO 031,Reach-1,7
Up Type=0
Dn Type=3
Dn Slope=0.005

--- LITTLE LLANO 031.g01 (geometry) ---

Geom Title=Existing Conditions

River Reach=LITTLE LLANO 031,Reach-1
Reach XY= 30
      2825420.00     10267674.00      2825254.25     10267485.00
      2825073.75     10266881.00      2824858.00     10266681.00
      2824736.25     10266456.00      2824776.75     10265903.00
      2824733.75     10265627.00      2824514.00     10265447.00
      2824576.25     10265210.00      2824353.75     10265107.00
      2824167.25     10265159.00      2824022.75     10265114.00
      2823686.00     10264833.00      2823396.50     10264401.00
      2823109.25     10264403.00      2822990.25     10264187.00
      2822814.75     10264101.00      2822538.75     10263781.00
      2822281.75     10263293.00      2822026.50     10263012.00
      2821866.75     10262962.00      2821648.00     10262612.00
      2821594.00     10262354.00      2821892.50     10261347.00
      2821795.75     10261099.00      2821646.50     10261062.00
      2821604.25     10260952.00      2821681.25     10260825.00
      2821952.50     10260663.00      2821948.50     10260604.00

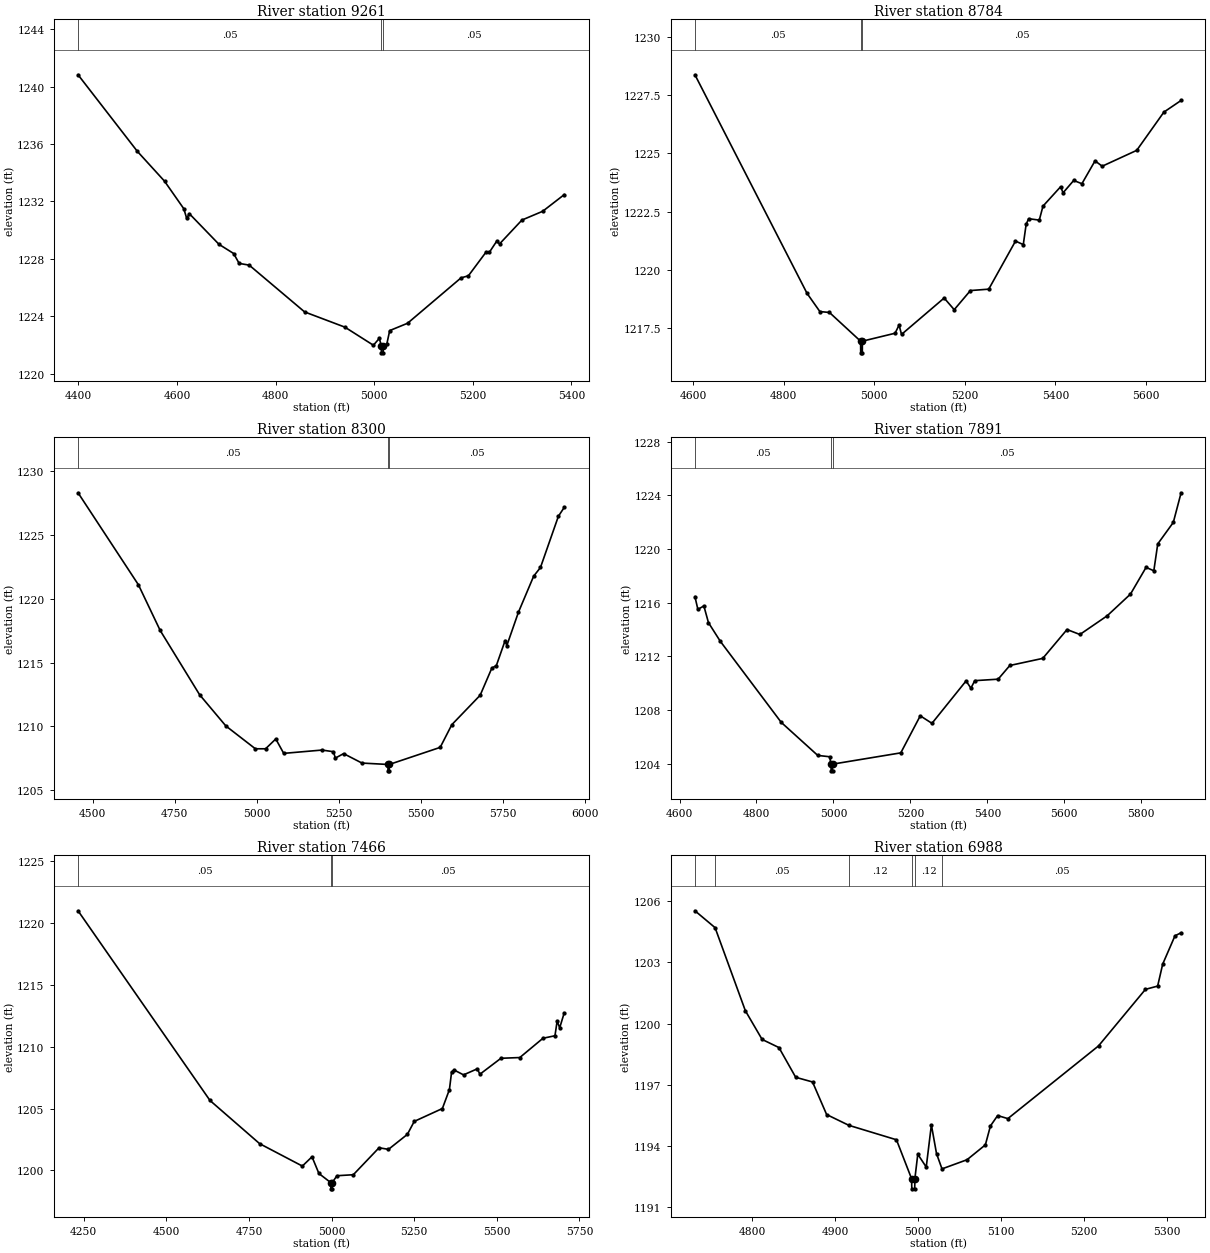
Type RM Length L Ch R = 1,9261,477,477,477
BEGIN DESCRIPTION:
LITTLE LLANO 031 19.0
END DESCRIPTION:
XS GIS Cut Line= 3
      2825805.66     10267453.11      2825217.50     10267331.00
      2825005.69     10267653.10
#Sta/Elev= 30
  4399.3 1240.82  4519.5 1235.49  4574.7 1233.41  4613.8 1231.49  4619.8 1230.81
  4624.9 1231.15  4685.2 1229.01  4714.9 1228.37  4726.1 1227.68  4746.5 1227.56
  4858.9 1224.30  4940.6 1223.24  4998.4 1221.98  5010.5 1222.46  5014.4 1221.95
  5014.7 1221.45  5018.2 1221.45  5018.4 1221.95  5025.5 1222.04  5031.5 1223.00
  5067.7 1223.51  5176.1 1226.67  5191.2 1226.82  5227.4 1228.49  5233.4 1228.44
  5248.4 1229.22  5254.4 1229.04  5299.7 1230.70  5341.8 1231.31  5385.5 1232.47
#Mann=3,-1,0
  4399.3    0.05       0  5014.4    0.03       0  5018.4    0.05       0
Bank Sta=5014.4,5018.4
Exp/Cntr=0.3,0.1

Type RM Length L Ch R = 1,8784,484,484,484
BEGIN DESCRIPTION:
LITTLE LLANO 031 18.0
END DESCRIPTION:
XS GIS Cut Line= 3
      2825355.71     10266603.09      2825073.75     10266881.00
      2824805.69     10267503.10
#Sta/Elev= 30
  4604.1 1228.37  4851.6 1219.00  4879.9 1218.22  4901.1 1218.18  4969.8 1216.95
  4970.1 1216.45  4973.6 1216.45  4973.8 1216.95  5045.9 1217.29  5054.8 1217.64
  5060.2 1217.24  5154.3 1218.80  5176.5 1218.30  5212.3 1219.12  5252.7 1219.18
  5311.8 1221.24  5329.0 1221.09  5335.3 1221.96  5340.8 1222.20  5364.3 1222.14
  5372.5 1222.74  5411.4 1223.57  5416.8 1223.31  5440.3 1223.84  5458.4 1223.70
  5487.4 1224.68  5503.2 1224.45  5579.4 1225.13  5639.4 1226.77  5677.4 1227.27
#Mann=3,-1,0
  4604.1    0.05       0  4969.8    0.03       0  4973.8    0.05       0
Bank Sta=4969.8,4973.8
Exp/Cntr=0.3,0.1

Type RM Length L Ch R = 1,8300,409,409,409
BEGIN DESCRIPTION:
LITTLE LLANO 031 17.0
END DESCRIPTION:
XS GIS Cut Line= 3
      2825305.65     10266503.11      2824761.25     10266518.00
      2823855.67     10266753.11
#Sta/Elev= 30
  4455.4 1228.32  4639.3 1221.10  4705.5 1217.52  4825.5 1212.48  4905.5 1210.03
  4995.3 1208.24  5026.4 1208.24  5057.4 1209.01  5081.6 1207.88  5198.1 1208.14
  5233.0 1208.01  5238.7 1207.51  5264.0 1207.86  5319.8 1207.12  5398.9 1207.01
  5399.2 1206.51  5402.7 1206.51  5402.9 1207.01  5558.0 1208.35  5593.4 1210.13
  5679.7 1212.44  5715.1 1214.56  5729.0 1214.77  5755.7 1216.73  5760.8 1216.33
  5796.2 1218.95  5842.6 1221.78  5863.3 1222.46  5917.9 1226.48  5935.6 1227.17
#Mann=3,-1,0
  4455.4    0.05       0  5398.9    0.03       0  5402.9    0.05       0
Bank Sta=5398.9,5402.9
Exp/Cntr=0.3,0.1

Type RM Length L Ch R = 1,7891,425,425,425
BEGIN DESCRIPTION:
LITTLE LLANO 031 16.0
END DESCRIPTION:
XS GIS Cut Line= 3
      2825055.69     10266303.12      2824748.75     10266115.00
      2823855.67     10266253.11
#Sta/Elev= 30
  4640.0 1216.45  4647.7 1215.50  4663.2 1215.76  4675.2 1214.51  4705.8 1213.13
  4864.4 1207.08  4959.2 1204.62  4990.0 1204.52  4993.9 1203.97  4994.1 1203.47
  4997.6 1203.47  4997.9 1203.97  5175.1 1204.81  5225.7 1207.57  5256.1 1207.01
  5344.8 1210.17  5357.3 1209.63  5367.4 1210.19  5428.1 1210.30  5458.5 1211.32
  5544.1 1211.85  5607.2 1214.00  5640.6 1213.63  5711.4 1215.02  5772.1 1216.64
  5812.6 1218.63  5832.8 1218.38  5843.0 1220.38  5883.4 1221.98  5903.7 1224.19
#Mann=3,-1,0
  4640.0    0.05       0  4993.9    0.03       0  4997.9    0.05       0
Bank Sta=4993.9,4997.9
Exp/Cntr=0.3,0.1

Type RM Length L Ch R = 1,7466,478,478,478
BEGIN DESCRIPTION:
LITTLE LLANO 031 15.0
END DESCRIPTION:
XS GIS Cut Line= 3
      2825355.67     10266153.10      2824740.25     10265695.00
      2824205.69     10266153.11
#Sta/Elev= 30
  4232.8 1220.98  4632.1 1205.65  4782.3 1202.16  4911.6 1200.35  4940.8 1201.10
  4961.7 1199.75  4997.7 1199.01  4998.0 1198.51  5001.5 1198.51  5001.7 1199.01
  5016.4 1199.57  5065.8 1199.65  5143.7 1201.83  5172.2 1201.70  5229.3 1202.91
  5250.2 1203.96  5335.3 1205.00  5356.6 1206.53  5363.2 1207.95  5370.9 1208.11
  5399.4 1207.72  5441.1 1208.21  5448.8 1207.77  5512.5 1209.06  5569.6 1209.12
  5639.8 1210.68  5676.0 1210.88  5682.6 1212.07  5690.3 1211.52  5704.0 1212.73
#Mann=3,-1,0
  4232.8    0.05       0  4997.7    0.05       0  5001.7    0.05       0
Bank Sta=4997.7,5001.7
Exp/Cntr=0.3,0.1

Type RM Length L Ch R = 1,6988,483,483,483
BEGIN DESCRIPTION:
LITTLE LLANO 031 14.0
END DESCRIPTION:
XS GIS Cut Line= 3
      2824805.72     10265303.11      2824540.00     10265345.00
      2824355.66     10265603.14
#Sta/Elev= 30
  4731.0 1205.54  4755.3 1204.71  4791.8 1200.63  4812.0 1199.22  4832.3 1198.82
  4852.5 1197.36  4872.8 1197.13  4889.8 1195.53  4916.6 1195.00  4974.0 1194.29
  4992.2 1192.38  4992.5 1191.88  4996.0 1191.88  4996.2 1192.38  4999.7 1193.58
  5009.9 1192.95  5016.1 1195.02  5022.3 1193.61  5028.9 1192.86  5059.1 1193.31
  5081.2 1194.04  5087.3 1194.97  5096.0 1195.48  5108.3 1195.33  5217.6 1198.90
  5274.2 1201.68  5288.9 1201.84  5295.0 1202.92  5309.8 1204.31  5317.2 1204.46
#Mann=6,-1,0
  4731.0    0.12       0  4755.3    0.05       0  4916.6    0.12       0
  4992.2    0.07       0  4996.2    0.12       0  5028.9    0.05       0
Bank Sta=4992.2,4996.2
Exp/Cntr=0.3,0.1

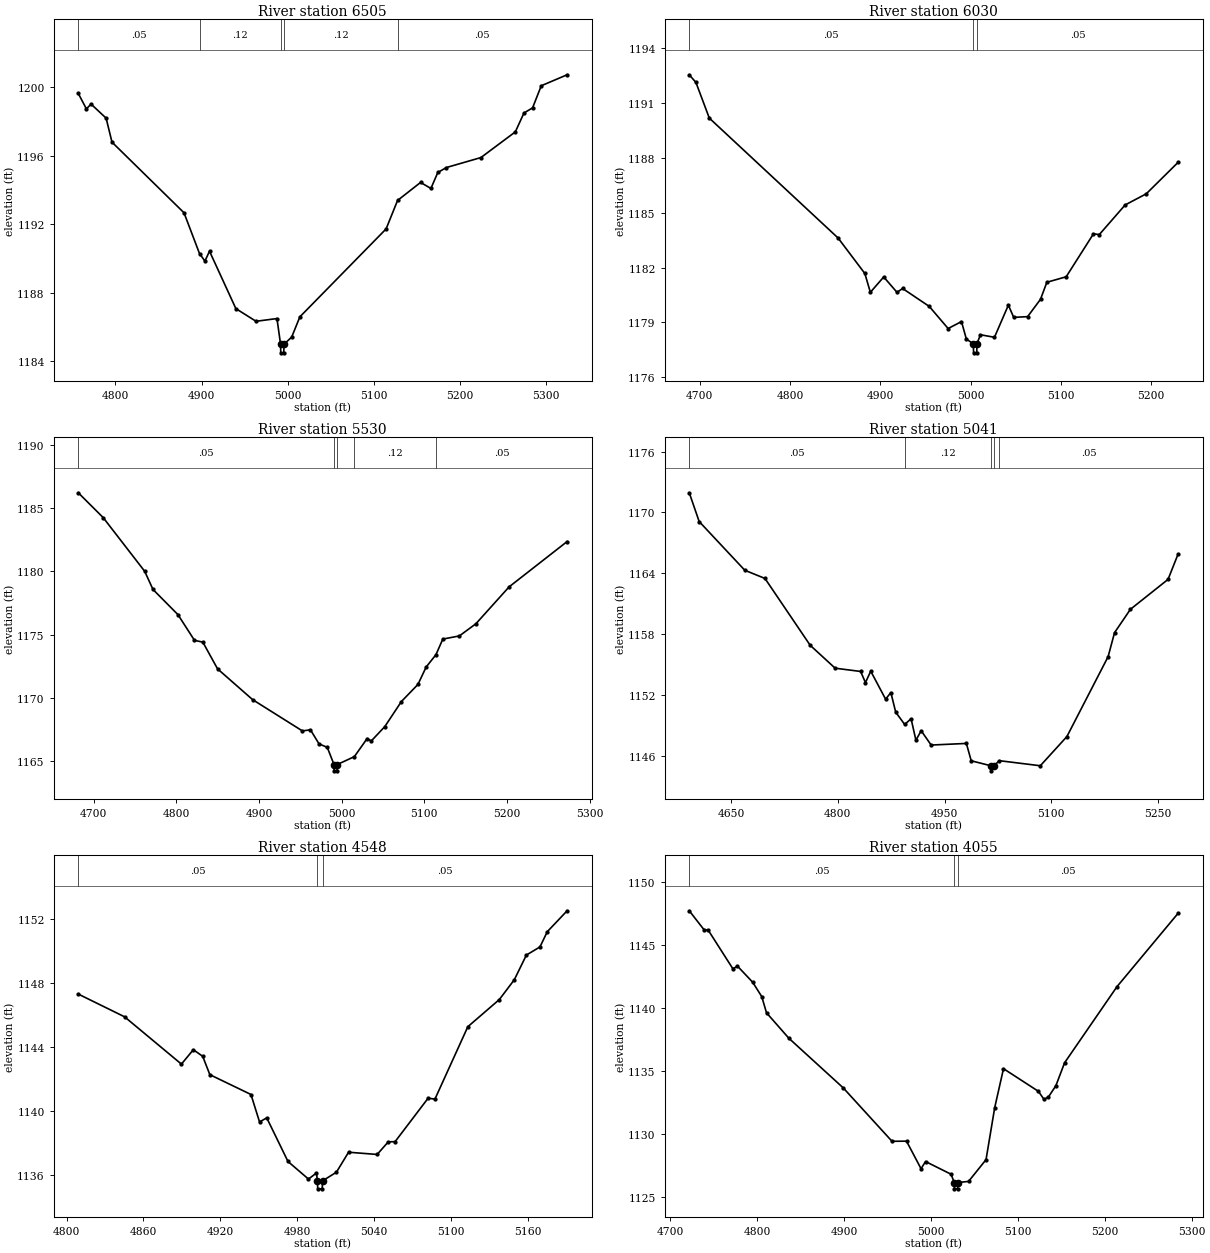
Type RM Length L Ch R = 1,6505,475,475,475
BEGIN DESCRIPTION:
LITTLE LLANO 031 13.0
END DESCRIPTION:
XS GIS Cut Line= 3
      2824355.67     10264903.14      2824265.75     10265129.00
      2824255.68     10265453.14
#Sta/Elev= 30
  4756.9 1199.62  4766.3 1198.72  4771.7 1199.00  4789.2 1198.18  4796.0 1196.78
  4879.6 1192.66  4897.6 1190.28  4903.9 1189.84  4909.2 1190.42  4939.8 1187.07
  4963.2 1186.33  4987.5 1186.49  4991.7 1184.99  4991.9 1184.49  4995.4 1184.49
  4995.7 1184.99  5004.6 1185.41  5014.1 1186.59  5114.2 1191.72  5127.5 1193.38
  5154.2 1194.43  5166.2 1194.08  5174.2 1195.01  5184.2 1195.30  5224.2 1195.88
  5264.2 1197.38  5274.2 1198.48  5284.2 1198.78  5294.3 1200.07  5324.3 1200.71
#Mann=5,-1,0
  4756.9    0.05       0  4897.6    0.12       0  4991.7    0.07       0
  4995.7    0.12       0  5127.5    0.05       0
Bank Sta=4991.7,4995.7
Exp/Cntr=0.3,0.1

Type RM Length L Ch R = 1,6030,500,500,500
BEGIN DESCRIPTION:
LITTLE LLANO 031 12.0
END DESCRIPTION:
XS GIS Cut Line= 3
      2824055.70     10264703.09      2823875.25     10264957.00
      2823755.68     10265153.12
#Sta/Elev= 30
  4688.5 1192.55  4695.9 1192.13  4710.7 1190.18  4853.3 1183.62  4882.9 1181.68
  4889.0 1180.65  4903.8 1181.49  4918.5 1180.65  4924.7 1180.86  4954.2 1179.88
  4975.1 1178.67  4989.9 1179.05  4995.3 1178.09  5003.0 1177.84  5003.3 1177.34
  5006.8 1177.34  5007.0 1177.84  5010.9 1178.33  5026.4 1178.19  5041.8 1179.95
  5047.7 1179.28  5063.1 1179.32  5077.4 1180.27  5084.4 1181.20  5105.8 1181.50
  5136.0 1183.85  5142.5 1183.81  5171.1 1185.43  5194.5 1186.04  5229.7 1187.76
#Mann=3,-1,0
  4688.5    0.05       0  5003.0    0.05       0  5007.0    0.05       0
Bank Sta=5003,5007
Exp/Cntr=0.3,0.1

Type RM Length L Ch R = 1,5530,489,489,489
BEGIN DESCRIPTION:
LITTLE LLANO 031 11.0
END DESCRIPTION:
XS GIS Cut Line= 3
      2823855.68     10264603.11      2823538.50     10264631.00
      2823555.69     10264903.16
#Sta/Elev= 30
  4681.6 1186.19  4711.7 1184.23  4761.9 1179.99  4771.9 1178.56  4802.1 1176.57
  4822.1 1174.54  4832.2 1174.40  4850.0 1172.29  4892.4 1169.86  4952.6 1167.39
  4962.3 1167.48  4972.7 1166.37  4982.7 1166.09  4990.8 1164.74  4991.0 1164.24
  4994.5 1164.24  4994.8 1164.74  5015.4 1165.36  5030.9 1166.79  5035.9 1166.60
  5052.2 1167.73  5072.3 1169.71  5092.3 1171.06  5102.3 1172.44  5114.1 1173.41
  5122.4 1174.64  5142.4 1174.89  5162.4 1175.85  5202.5 1178.76  5272.7 1182.34
#Mann=5,-1,0
  4681.6    0.05       0  4990.8    0.05       0  4994.8    0.05       0
  5015.4    0.12       0  5114.1    0.05       0
Bank Sta=4990.8,4994.8
Exp/Cntr=0.3,0.1

Type RM Length L Ch R = 1,5041,493,493,493
BEGIN DESCRIPTION:
LITTLE LLANO 031 10.0
END DESCRIPTION:
XS GIS Cut Line= 3
      2823505.72     10264153.08      2823205.00     10264430.00
      2822955.64     10264553.13
#Sta/Elev= 30
  4591.2 1171.94  4605.1 1169.11  4669.2 1164.31  4697.6 1163.50  4761.1 1156.92
  4796.2 1154.66  4832.0 1154.34  4838.8 1153.24  4846.2 1154.37  4867.1 1151.61
  4874.5 1152.26  4881.3 1150.33  4893.9 1149.12  4902.9 1149.68  4909.7 1147.57
  4917.1 1148.50  4931.1 1147.09  4980.6 1147.25  4987.4 1145.54  5015.1 1145.05
  5015.4 1144.55  5019.1 1145.05  5027.1 1145.55  5084.5 1145.05  5121.9 1147.93
  5179.8 1155.80  5188.8 1158.16  5211.1 1160.46  5264.0 1163.41  5278.1 1165.90
#Mann=5,-1,0
  4591.2    0.05       0  4893.9    0.12       0  5015.1    0.07       0
  5019.1    0.12       0  5027.1    0.05       0
Bank Sta=5015.1,5019.1
Exp/Cntr=0.3,0.1

Type RM Length L Ch R = 1,4548,493,493,493
BEGIN DESCRIPTION:
LITTLE LLANO 031 9.0
END DESCRIPTION:
XS GIS Cut Line= 3
      2822955.67     10263953.15      2822868.75     10264123.00
      2822805.70     10264303.08
#Sta/Elev= 30
  4809.2 1147.29  4845.3 1145.87  4889.7 1142.91  4899.0 1143.81  4906.3 1143.40
  4911.9 1142.25  4944.0 1141.01  4950.7 1139.29  4956.3 1139.55  4972.9 1136.82
  4988.9 1135.72  4995.1 1136.10  4995.9 1135.61  4996.1 1135.11  4999.6 1135.11
  4999.9 1135.61  5010.7 1136.15  5020.2 1137.40  5042.5 1137.26  5051.2 1138.05
  5056.5 1138.06  5082.3 1140.78  5087.6 1140.72  5113.3 1145.25  5137.9 1146.95
  5149.6 1148.19  5159.0 1149.73  5169.6 1150.24  5175.3 1151.19  5190.8 1152.50
#Mann=3,-1,0
  4809.2    0.05       0  4995.9    0.05       0  4999.9    0.05       0
Bank Sta=4995.9,4999.9
Exp/Cntr=0.3,0.1

Type RM Length L Ch R = 1,4055,478,478,478
BEGIN DESCRIPTION:
LITTLE LLANO 031 8.0
END DESCRIPTION:
XS GIS Cut Line= 3
      2822805.72     10263703.10      2822538.75     10263781.00
      2822255.72     10263753.12
#Sta/Elev= 30
  4721.9 1147.73  4738.7 1146.24  4743.9 1146.17  4772.1 1143.12  4777.4 1143.33
  4794.9 1142.05  4805.3 1140.91  4810.8 1139.62  4836.5 1137.60  4899.0 1133.66
  4955.2 1129.41  4971.9 1129.42  4988.6 1127.23  4993.8 1127.80  5023.2 1126.79
  5026.8 1126.13  5027.1 1125.63  5030.6 1125.63  5030.8 1126.13  5043.3 1126.22
  5063.4 1127.95  5073.4 1132.09  5083.5 1135.18  5123.7 1133.38  5130.1 1132.74
  5135.1 1132.92  5143.8 1133.83  5153.8 1135.65  5214.1 1141.70  5284.4 1147.53
#Mann=3,-1,0
  4721.9    0.05       0  5026.8    0.05       0  5030.8    0.05       0
Bank Sta=5026.8,5030.8
Exp/Cntr=0.3,0.1

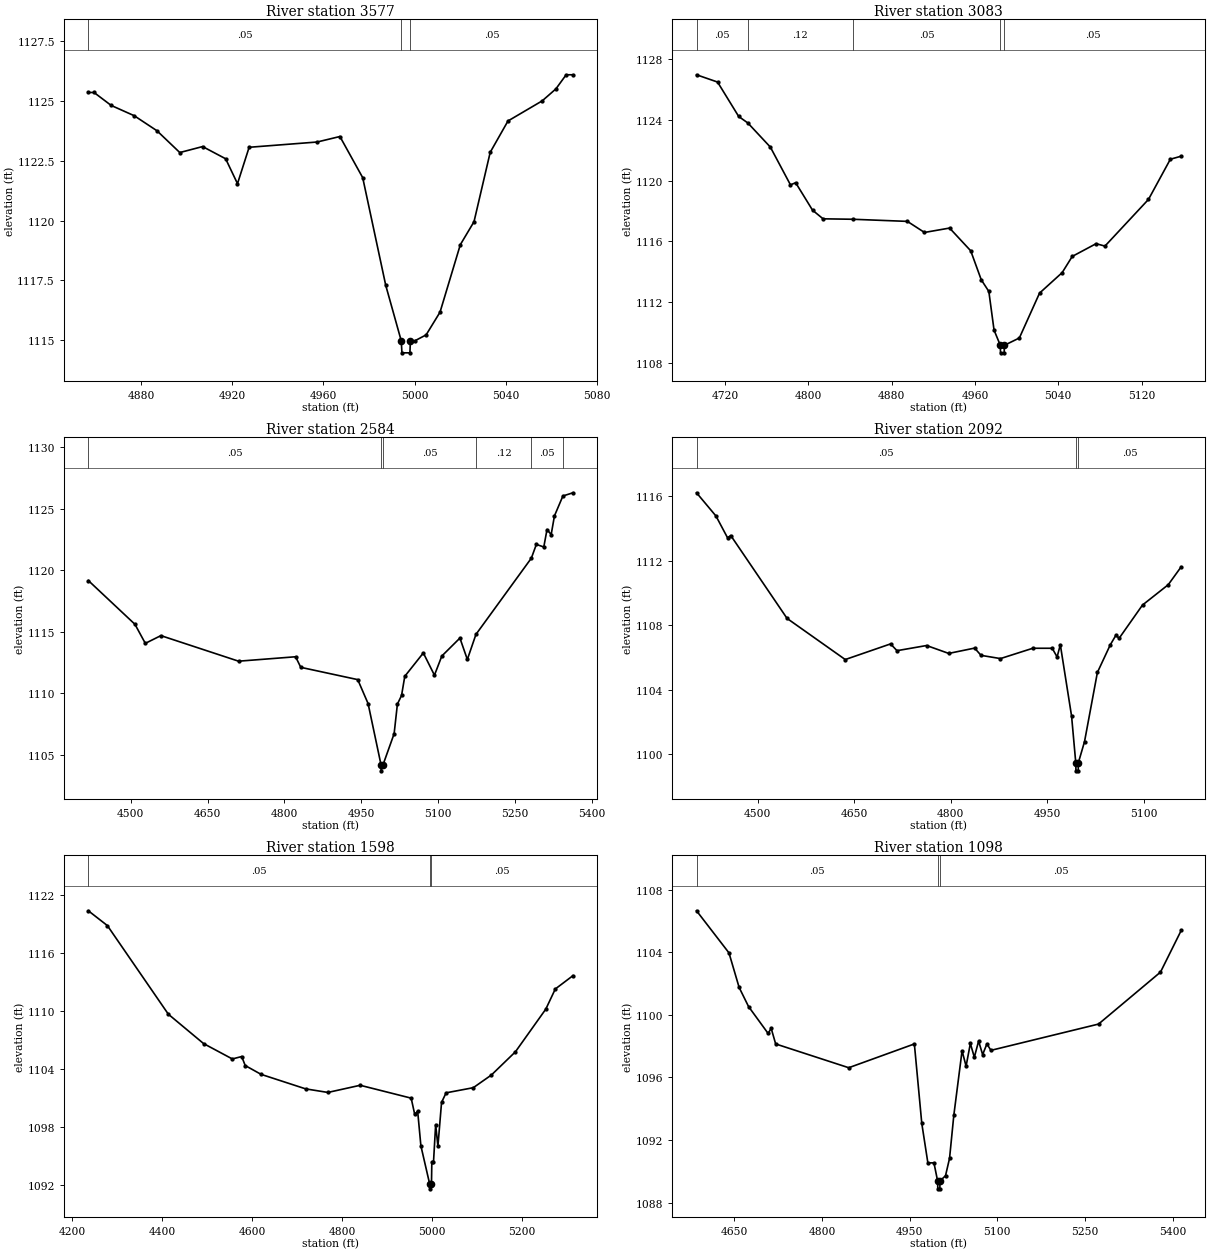
Type RM Length L Ch R = 1,3577,494,494,494
BEGIN DESCRIPTION:
LITTLE LLANO 031 7.0
END DESCRIPTION:
XS GIS Cut Line= 3
      2822455.69     10263353.11      2822313.00     10263364.00
      2822255.68     10263403.12
#Sta/Elev= 29
  4856.9 1125.35  4859.4 1125.35  4866.9 1124.81  4877.0 1124.38  4887.0 1123.75
  4897.0 1122.84  4907.0 1123.09  4917.1 1122.58  4922.3 1121.54  4927.4 1123.06
  4957.2 1123.28  4967.2 1123.51  4977.2 1121.79  4987.3 1117.29  4994.1 1114.97
  4994.4 1114.47  4997.9 1114.47  4998.1 1114.97  5000.0 1114.97  5005.0 1115.22
  5011.1 1116.17  5020.0 1118.99  5026.0 1119.95  5033.1 1122.85  5040.9 1124.16
  5055.9 1125.00  5061.9 1125.50  5066.4 1126.09  5069.4 1126.09
#Mann=3,-1,0
  4856.9    0.05       0  4994.1    0.03       0  4998.1    0.05       0
Bank Sta=4994.1,4998.1
Exp/Cntr=0.3,0.1

Type RM Length L Ch R = 1,3083,499,499,499
BEGIN DESCRIPTION:
LITTLE LLANO 031 6.0
END DESCRIPTION:
XS GIS Cut Line= 3
      2822305.64     10262953.12      2822002.25     10263002.00
      2821955.69     10263153.09
#Sta/Elev= 30
  4692.7 1126.98  4712.9 1126.50  4733.2 1124.23  4742.0 1123.80  4763.6 1122.21
  4782.9 1119.72  4787.9 1119.86  4804.1 1118.05  4814.2 1117.48  4842.8 1117.45
  4895.2 1117.31  4911.6 1116.58  4935.7 1116.87  4956.0 1115.37  4966.1 1113.46
  4973.4 1112.69  4978.4 1110.14  4984.4 1109.14  4984.6 1108.64  4988.1 1108.64
  4988.4 1109.14  5002.7 1109.62  5022.1 1112.58  5043.8 1113.93  5053.5 1115.00
  5076.4 1115.84  5084.9 1115.68  5126.7 1118.76  5147.7 1121.41  5158.1 1121.61
#Mann=5,-1,0
  4692.7    0.05       0  4742.0    0.12       0  4842.8    0.05       0
  4984.4    0.05       0  4988.4    0.05       0
Bank Sta=4984.4,4988.4
Exp/Cntr=0.3,0.1

Type RM Length L Ch R = 1,2584,492,492,492
BEGIN DESCRIPTION:
LITTLE LLANO 031 5.0
END DESCRIPTION:
XS GIS Cut Line= 3
      2822255.70     10262753.11      2821679.50     10262667.00
      2821455.66     10262953.15
#Sta/Elev= 30
  4417.4 1119.17  4508.4 1115.61  4528.6 1114.06  4559.0 1114.69  4710.6 1112.61
  4821.9 1112.97  4832.0 1112.11  4943.2 1111.11  4963.4 1109.16  4988.6 1104.19
  4988.8 1103.69  4992.6 1104.19  5014.2 1106.71  5020.6 1109.12  5028.7 1109.82
  5035.0 1111.38  5071.2 1113.28  5092.9 1111.47  5107.3 1113.03  5142.6 1114.49
  5157.1 1112.75  5173.9 1114.79  5282.0 1120.99  5291.8 1122.11  5306.3 1121.90
  5312.6 1123.32  5320.7 1122.91  5327.1 1124.43  5343.6 1126.05  5363.3 1126.31
#Mann=6,-1,0
  4417.4    0.05       0  4988.6    0.05       0  4992.6    0.05       0
  5173.9    0.12       0  5282.0    0.05       0  5343.6    0.12       0
Bank Sta=4988.6,4992.6
Exp/Cntr=0.3,0.1

Type RM Length L Ch R = 1,2092,494,494,494
BEGIN DESCRIPTION:
LITTLE LLANO 031 4.0
END DESCRIPTION:
XS GIS Cut Line= 3
      2822255.70     10262303.11      2821663.75     10262245.00
      2821505.66     10262253.11
#Sta/Elev= 30
  4405.2 1116.21  4435.4 1114.77  4453.4 1113.42  4458.4 1113.56  4545.9 1108.42
  4636.3 1105.87  4706.7 1106.84  4716.7 1106.42  4762.7 1106.74  4797.1 1106.25
  4837.3 1106.58  4847.3 1106.13  4877.5 1105.93  4927.7 1106.57  4957.9 1106.57
  4965.5 1106.03  4970.5 1106.79  4988.0 1102.36  4994.5 1099.47  4994.8 1098.97
  4998.3 1098.97  4998.5 1099.47  5008.1 1100.78  5028.1 1105.07  5048.1 1106.78
  5056.9 1107.38  5061.9 1107.19  5098.2 1109.25  5138.2 1110.51  5158.3 1111.62
#Mann=3,-1,0
  4405.2    0.05       0  4994.5    0.05       0  4998.5    0.05       0
Bank Sta=4994.5,4998.5
Exp/Cntr=0.3,0.1

Type RM Length L Ch R = 1,1598,500,500,500
BEGIN DESCRIPTION:
LITTLE LLANO 031 3.0
END DESCRIPTION:
XS GIS Cut Line= 3
      2822355.66     10262253.09      2821766.25     10261767.00
      2821455.64     10261803.12
#Sta/Elev= 30
  4236.0 1120.38  4278.3 1118.85  4413.8 1109.69  4492.0 1106.66  4555.9 1105.07
  4576.7 1105.32  4584.5 1104.39  4619.7 1103.48  4718.7 1101.98  4768.2 1101.61
  4839.9 1102.35  4953.2 1101.02  4961.1 1099.34  4967.6 1099.68  4974.8 1096.09
  4994.3 1092.15  4994.5 1091.65  4998.3 1092.15  4999.1 1094.41  5002.8 1094.41
  5007.6 1098.29  5012.6 1096.05  5020.7 1100.58  5030.8 1101.57  5091.2 1102.10
  5131.4 1103.41  5184.8 1105.81  5252.3 1110.22  5273.4 1112.30  5312.7 1113.68
#Mann=3,-1,0
  4236.0    0.05       0  4994.3    0.05       0  4998.3    0.05       0
Bank Sta=4994.3,4998.3
Exp/Cntr=0.3,0.1

Type RM Length L Ch R = 1,1098,494,494,494
BEGIN DESCRIPTION:
LITTLE LLANO 031 2.0
END DESCRIPTION:
XS GIS Cut Line= 3
      2822255.72     10261203.10      2821857.75     10261319.00
      2821555.67     10261603.12
#Sta/Elev= 30
  4585.5 1106.65  4641.0 1103.96  4658.4 1101.75  4674.5 1100.53  4708.0 1098.81
  4713.2 1099.14  4720.9 1098.14  4845.9 1096.62  4958.2 1098.14  4970.9 1093.06
  4981.3 1090.54  4991.7 1090.54  4998.0 1089.38  4998.3 1088.88  5001.8 1088.88
  5002.0 1089.38  5011.5 1089.72  5018.4 1090.83  5025.7 1093.58  5039.8 1097.70
  5046.7 1096.72  5054.0 1098.17  5060.8 1097.29  5068.1 1098.32  5075.0 1097.46
  5082.3 1098.14  5089.2 1097.73  5273.3 1099.41  5379.3 1102.73  5414.7 1105.39
#Mann=3,-1,0
  4585.5    0.05       0  4998.0    0.05       0  5002.0    0.05       0
Bank Sta=4998,5002
Exp/Cntr=0.3,0.1

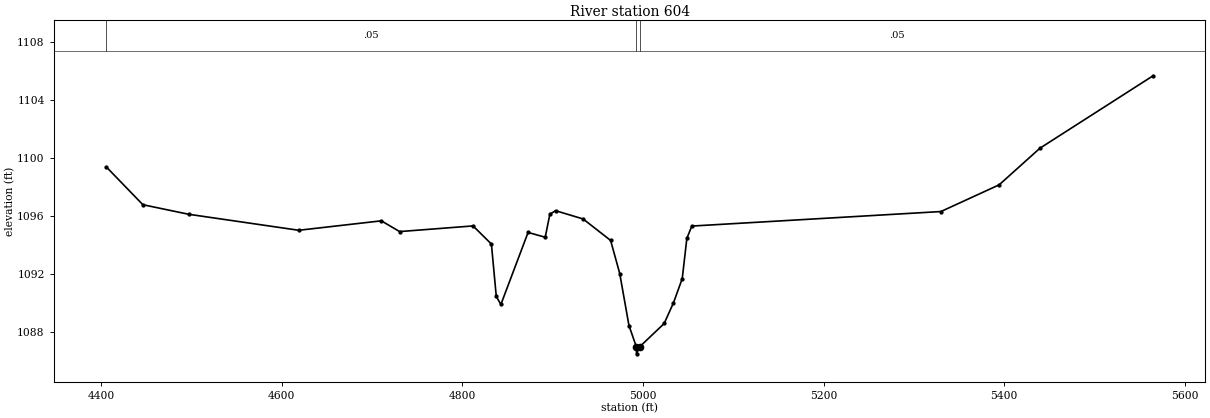
Type RM Length L Ch R = 1,604,0,0,0
BEGIN DESCRIPTION:
LITTLE LLANO 031 1.0
END DESCRIPTION:
XS GIS Cut Line= 3
      2822205.69     10261103.11      2821620.50     10261000.00
      2821505.68     10261553.11
#Sta/Elev= 30
  4405.8 1099.37  4446.4 1096.76  4497.3 1096.10  4619.0 1095.00  4710.4 1095.65
  4730.7 1094.91  4812.0 1095.30  4832.3 1094.05  4837.7 1090.44  4842.8 1089.89
  4872.9 1094.85  4891.9 1094.52  4897.0 1096.10  4903.3 1096.35  4933.8 1095.78
  4964.3 1094.30  4974.4 1092.02  4984.6 1088.44  4992.7 1086.99  4993.0 1086.49
  4996.7 1086.99  5023.6 1088.58  5033.8 1089.99  5043.6 1091.67  5048.7 1094.44
  5054.2 1095.29  5330.0 1096.29  5394.5 1098.13  5439.6 1100.65  5564.9 1105.64
#Mann=3,-1,0
  4405.8    0.05       0  4992.7    0.03       0  4996.7    0.05       0
Bank Sta=4992.7,4996.7
Exp/Cntr=0.3,0.1

Chan Stop Cuts=-1