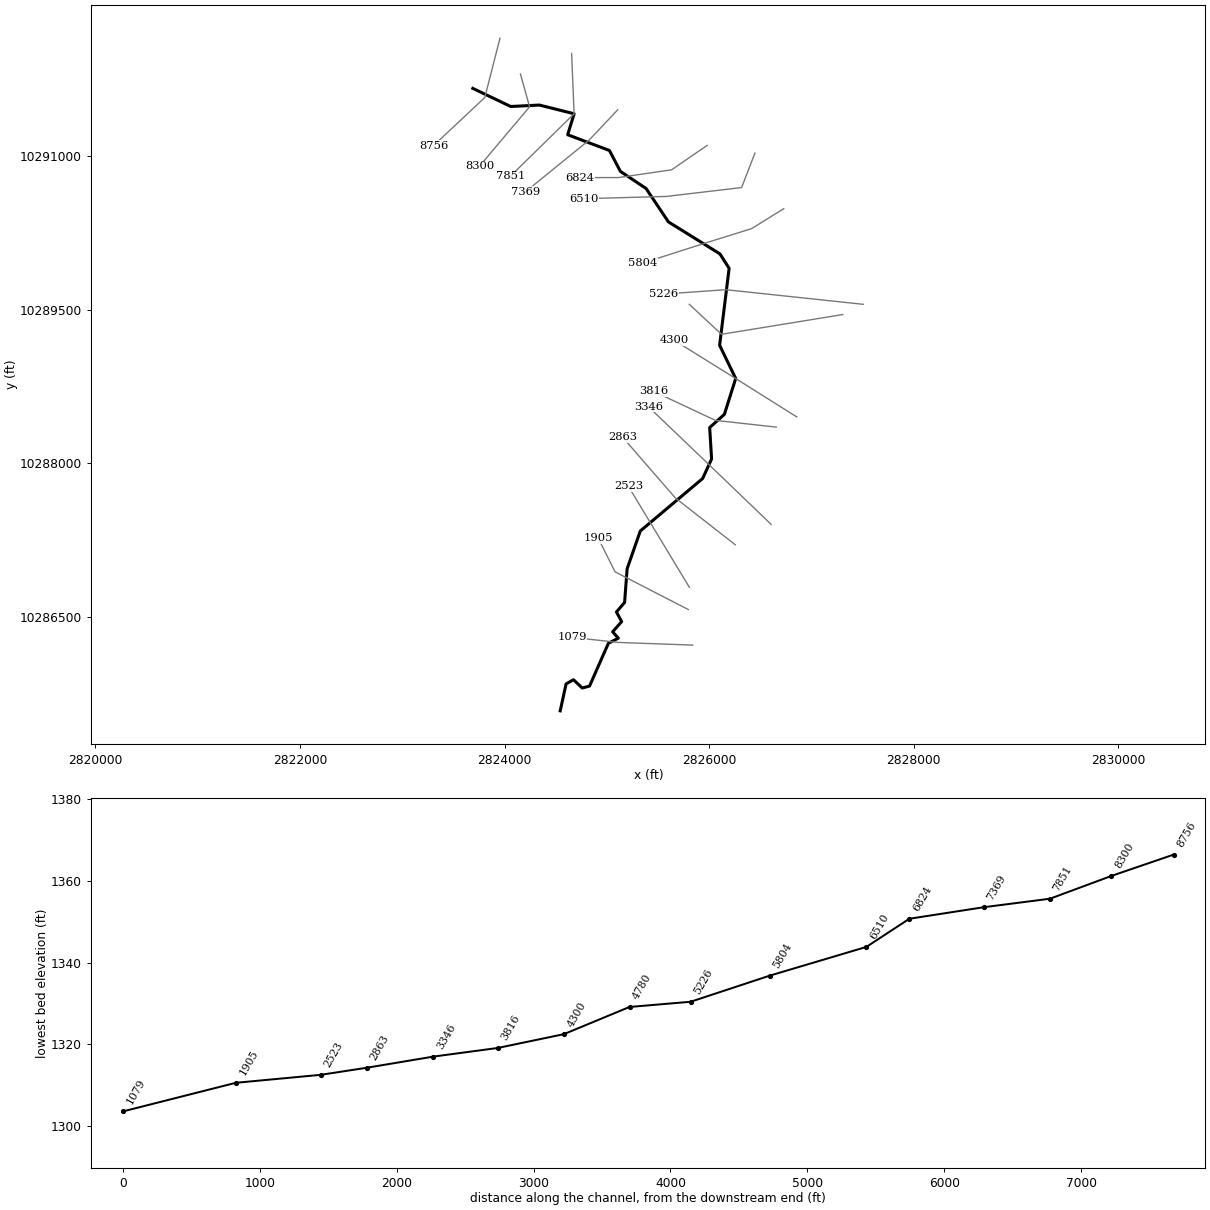
--- LITTLE LLANO 034.prj (project) ---

Proj Title=LITTLE LLANO 034 Base Level Engineering
Current Plan=p01
Default Exp/Contr=0.3,0.1
English Units
Geom File=g01
Flow File=f01
Plan File=p01
BEGIN DESCRIPTION:
LITTLE LLANO 034
END DESCRIPTION:

--- LITTLE LLANO 034.p01 (plan) ---

Plan Title=Multiple Run
Short Identifier=Multiple
Geom File=g01
Flow File=f01
Subcritical Flow
K Sum by GR= 0
Std Step Tol= 0.01
Critical Tol= 0.01
Num of Std Step Trials= 20
Max Error Tol= 0.3
Flow Tol Ratio= 0.001
Split Flow NTrial= 30
Split Flow Tol= 0.02
Split Flow Ratio= 0.02
Log Output Level= 0
Friction Slope Method= 1
Unsteady Friction Slope Method= 2
Unsteady Bridges Friction Slope Method= 1
Parabolic Critical Depth
Global Vel Dist=  1 , 1 , 1
Global Log Level= 0
CheckData=True
Encroach Param= -1, 0, 0, 0
BEGIN DESCRIPTION:
Multiple Run
END DESCRIPTION:

--- LITTLE LLANO 034.f01 (steady flow) ---

Flow Title=Multiple
Number of Profiles=7
Profile Names=10-year,25-year,50-year,1pct_min,100-year,1pct_plu,500-year
River Rch & RM= LITTLE LLANO 034,Reach-1,8756
      63     120     188      97     293     886     770
Boundary for River Rch & Prof#=LITTLE LLANO 034,Reach-1,1
Up Type=0
Dn Type=3
Dn Slope=0.005
Boundary for River Rch & Prof#=LITTLE LLANO 034,Reach-1,2
Up Type=0
Dn Type=3
Dn Slope=0.005
Boundary for River Rch & Prof#=LITTLE LLANO 034,Reach-1,3
Up Type=0
Dn Type=3
Dn Slope=0.005
Boundary for River Rch & Prof#=LITTLE LLANO 034,Reach-1,4
Up Type=0
Dn Type=3
Dn Slope=0.005
Boundary for River Rch & Prof#=LITTLE LLANO 034,Reach-1,5
Up Type=0
Dn Type=3
Dn Slope=0.005
Boundary for River Rch & Prof#=LITTLE LLANO 034,Reach-1,6
Up Type=0
Dn Type=3
Dn Slope=0.005
Boundary for River Rch & Prof#=LITTLE LLANO 034,Reach-1,7
Up Type=0
Dn Type=3
Dn Slope=0.005

--- LITTLE LLANO 034.g01 (geometry) ---

Geom Title=Existing Conditions

River Reach=LITTLE LLANO 034,Reach-1
Reach XY= 30
      2823690.00     10291663.00      2824060.75     10291486.00
      2824340.75     10291500.00      2824680.25     10291415.00
      2824617.25     10291210.00      2825025.50     10291056.00
      2825132.50     10290852.00      2825383.25     10290685.00
      2825602.25     10290358.00      2826105.00     10290046.00
      2826195.00     10289905.00      2826102.25     10289153.00
      2826259.25     10288828.00      2826148.75     10288478.00
      2826005.00     10288349.00      2826023.75     10288042.00
      2825936.25     10287851.00      2825326.75     10287338.00
      2825198.25     10286969.00      2825173.50     10286640.00
      2825093.75     10286547.00      2825144.75     10286453.00
      2825056.75     10286353.00      2825112.25     10286291.00
      2825015.00     10286241.00      2824831.00     10285823.00
      2824759.50     10285804.00      2824674.00     10285885.00
      2824601.75     10285844.00      2824544.25     10285581.00

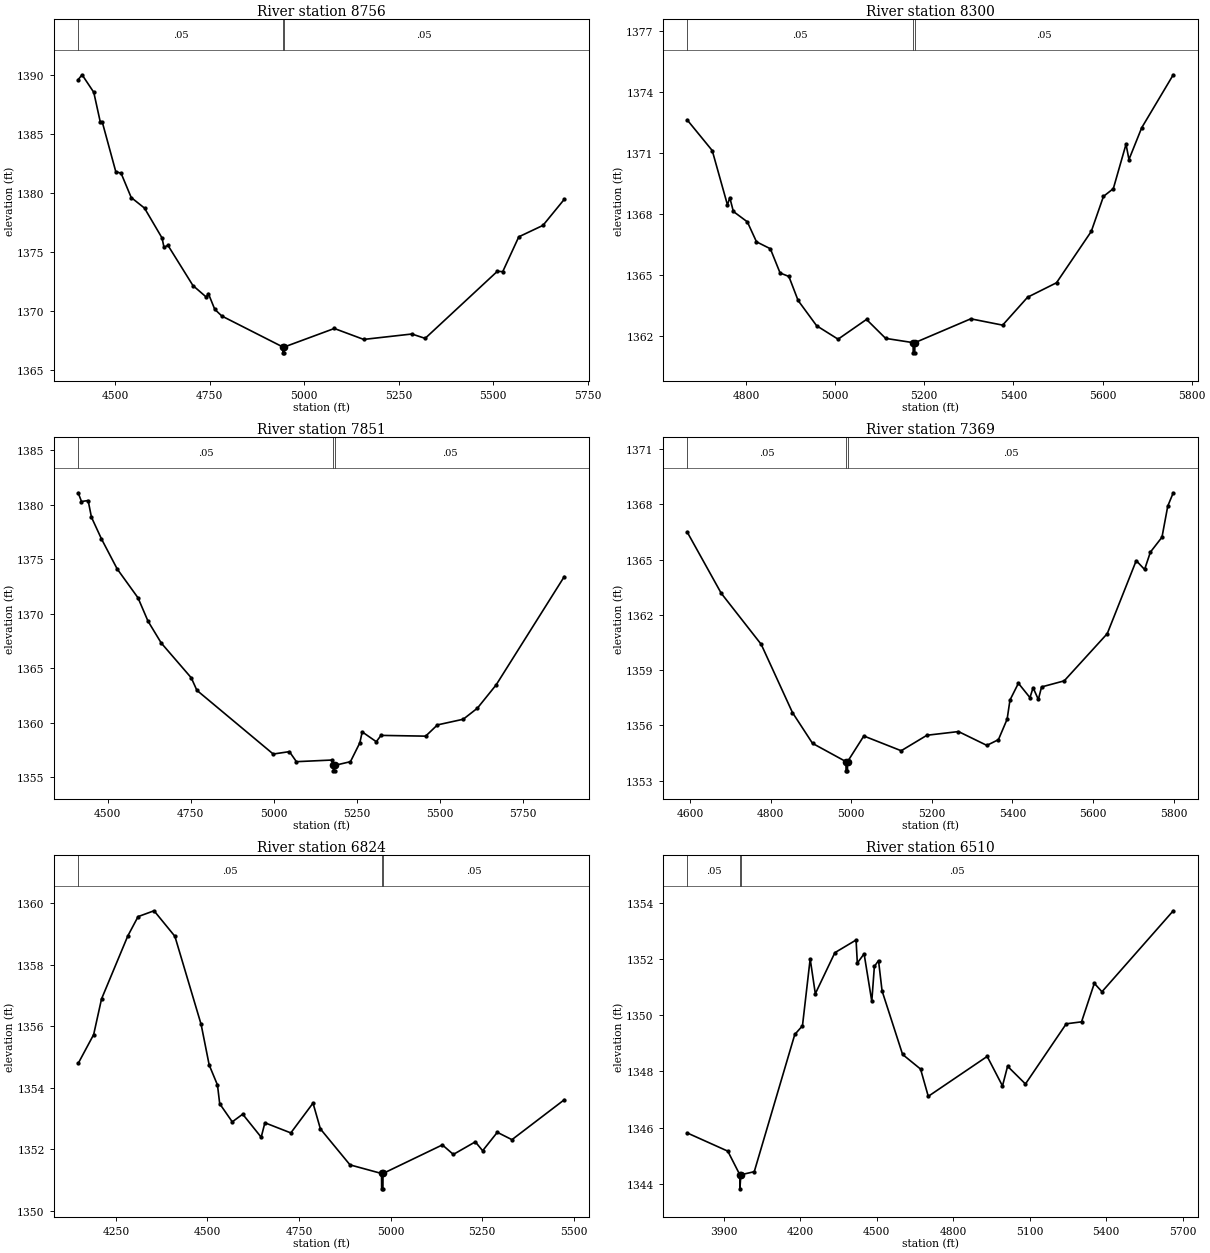
Type RM Length L Ch R = 1,8756,456,456,456
BEGIN DESCRIPTION:
LITTLE LLANO 034 15.0
END DESCRIPTION:
XS GIS Cut Line= 3
      2823955.69     10292153.14      2823807.50     10291574.00
      2823305.65     10291103.08
#Sta/Elev= 30
  4402.2 1389.64  4412.6 1390.05  4443.5 1388.56  4460.9 1386.01  4466.0 1386.03
  4501.7 1381.82  4515.8 1381.68  4542.5 1379.62  4577.7 1378.72  4624.1 1376.18
  4629.3 1375.38  4639.6 1375.56  4705.8 1372.14  4741.4 1371.15  4746.6 1371.46
  4763.5 1370.12  4782.2 1369.55  4943.5 1366.92  4943.7 1366.42  4947.2 1366.42
  4947.5 1366.92  5079.8 1368.49  5157.5 1367.56  5284.9 1368.02  5320.1 1367.65
  5511.1 1373.35  5525.3 1373.32  5567.8 1376.28  5631.7 1377.25  5688.2 1379.47
#Mann=3,-1,0
  4402.2    0.05       0  4943.5    0.03       0  4947.5    0.05       0
Bank Sta=4943.5,4947.5
Exp/Cntr=0.3,0.1

Type RM Length L Ch R = 1,8300,449,449,449
BEGIN DESCRIPTION:
LITTLE LLANO 034 14.0
END DESCRIPTION:
XS GIS Cut Line= 3
      2824155.69     10291803.07      2824245.00     10291483.00
      2823755.72     10290903.15
#Sta/Elev= 30
  4667.7 1372.63  4724.1 1371.12  4758.3 1368.45  4763.5 1368.81  4771.5 1368.13
  4802.9 1367.62  4823.4 1366.64  4854.5 1366.30  4876.4 1365.11  4896.1 1364.94
  4916.8 1363.76  4958.4 1362.52  5006.5 1361.86  5070.3 1362.83  5113.2 1361.90
  5174.9 1361.69  5175.1 1361.19  5178.6 1361.19  5178.9 1361.69  5304.3 1362.86
  5375.8 1362.55  5431.8 1363.92  5496.7 1364.63  5574.7 1367.15  5602.1 1368.87
  5624.2 1369.25  5652.7 1371.43  5659.3 1370.68  5687.9 1372.24  5758.7 1374.84
#Mann=3,-1,0
  4667.7    0.05       0  5174.9    0.03       0  5178.9    0.05       0
Bank Sta=5174.9,5178.9
Exp/Cntr=0.3,0.1

Type RM Length L Ch R = 1,7851,482,482,482
BEGIN DESCRIPTION:
LITTLE LLANO 034 13.0
END DESCRIPTION:
XS GIS Cut Line= 3
      2824655.69     10292003.09      2824680.25     10291415.00
      2824055.65     10290803.08
#Sta/Elev= 30
  4411.4 1381.10  4421.4 1380.30  4441.4 1380.39  4451.4 1378.86  4481.4 1376.88
  4528.8 1374.12  4591.5 1371.47  4621.6 1369.33  4661.6 1367.32  4751.7 1364.14
  4768.7 1362.99  4998.4 1357.15  5047.1 1357.37  5068.2 1356.45  5174.3 1356.60
  5179.3 1356.11  5179.6 1355.61  5183.1 1355.61  5183.3 1356.11  5230.8 1356.45
  5259.1 1358.18  5266.2 1359.18  5308.6 1358.28  5322.8 1358.86  5457.1 1358.79
  5492.5 1359.82  5570.2 1360.34  5612.7 1361.35  5669.3 1363.49  5874.4 1373.42
#Mann=3,-1,0
  4411.4    0.05       0  5179.3    0.03       0  5183.3    0.05       0
Bank Sta=5179.3,5183.3
Exp/Cntr=0.3,0.1

Type RM Length L Ch R = 1,7369,545,545,545
BEGIN DESCRIPTION:
LITTLE LLANO 034 12.0
END DESCRIPTION:
XS GIS Cut Line= 3
      2825105.67     10291453.10      2824826.00     10291157.00
      2824205.67     10290653.10
#Sta/Elev= 30
  4592.7 1366.50  4677.4 1363.17  4776.6 1360.40  4854.2 1356.70  4904.0 1355.03
  4986.9 1354.04  4987.2 1353.54  4990.7 1353.54  4990.9 1354.04  5031.3 1355.43
  5124.0 1354.63  5187.9 1355.47  5266.2 1355.67  5336.6 1354.92  5365.3 1355.23
  5386.9 1356.34  5394.0 1357.38  5414.9 1358.29  5443.6 1357.51  5451.3 1358.05
  5464.4 1357.41  5472.4 1358.09  5528.6 1358.42  5635.4 1360.98  5707.3 1364.94
  5728.1 1364.46  5742.4 1365.40  5771.2 1366.21  5785.6 1367.90  5799.2 1368.62
#Mann=3,-1,0
  4592.7    0.05       0  4986.9    0.03       0  4990.9    0.05       0
Bank Sta=4986.9,4990.9
Exp/Cntr=0.3,0.1

Type RM Length L Ch R = 1,6824,314,314,314
BEGIN DESCRIPTION:
Mapping XS 77ef0d20
END DESCRIPTION:
XS GIS Cut Line= 4
      2825980.53     10291106.16      2825633.33     10290867.46
      2825112.50     10290791.50      2824732.68     10290791.50
#Sta/Elev= 30
  4147.1 1354.79  4189.4 1355.73  4210.9 1356.89  4282.6 1358.94  4310.7 1359.57
  4354.3 1359.76  4411.2 1358.93  4482.9 1356.06  4504.9 1354.74  4527.5 1354.09
  4533.6 1353.48  4567.9 1352.89  4596.4 1353.14  4646.9 1352.39  4657.0 1352.86
  4727.8 1352.53  4788.4 1353.50  4808.6 1352.66  4889.4 1351.49  4975.5 1351.21
  4975.8 1350.71  4979.3 1350.71  4979.5 1351.21  5141.6 1352.14  5171.6 1351.83
  5231.6 1352.24  5251.6 1351.95  5291.6 1352.55  5331.6 1352.31  5474.6 1353.61
#Mann=3,-1,0
  4147.1    0.05       0  4975.5    0.03       0  4979.5    0.05       0
Bank Sta=4975.5,4979.5
Exp/Cntr=0.3,0.1

Type RM Length L Ch R = 1,6510,706,706,706
BEGIN DESCRIPTION:
Mapping XS 030669e4
END DESCRIPTION:
XS GIS Cut Line= 4
      2826447.12     10291030.18      2826316.93     10290693.84
      2825579.08     10290607.04      2824776.16     10290585.34
#Sta/Elev= 30
  3756.7 1345.81  3916.4 1345.16  3963.5 1344.32  3963.8 1343.82  3967.5 1344.32
  4020.1 1344.43  4179.0 1349.31  4209.2 1349.62  4239.4 1352.00  4259.6 1350.76
  4336.3 1352.22  4419.4 1352.67  4424.4 1351.85  4450.9 1352.18  4481.1 1350.49
  4491.2 1351.73  4507.5 1351.94  4521.4 1350.86  4601.9 1348.60  4672.4 1348.08
  4702.6 1347.11  4933.7 1348.53  4993.7 1347.48  5013.7 1348.18  5083.8 1347.55
  5243.8 1349.69  5303.8 1349.76  5353.9 1351.13  5383.9 1350.83  5663.5 1353.71
#Mann=3,-1,0
  3756.7    0.05       0  3963.5    0.03       0  3967.5    0.05       0
Bank Sta=3963.5,3967.5
Exp/Cntr=0.3,0.1

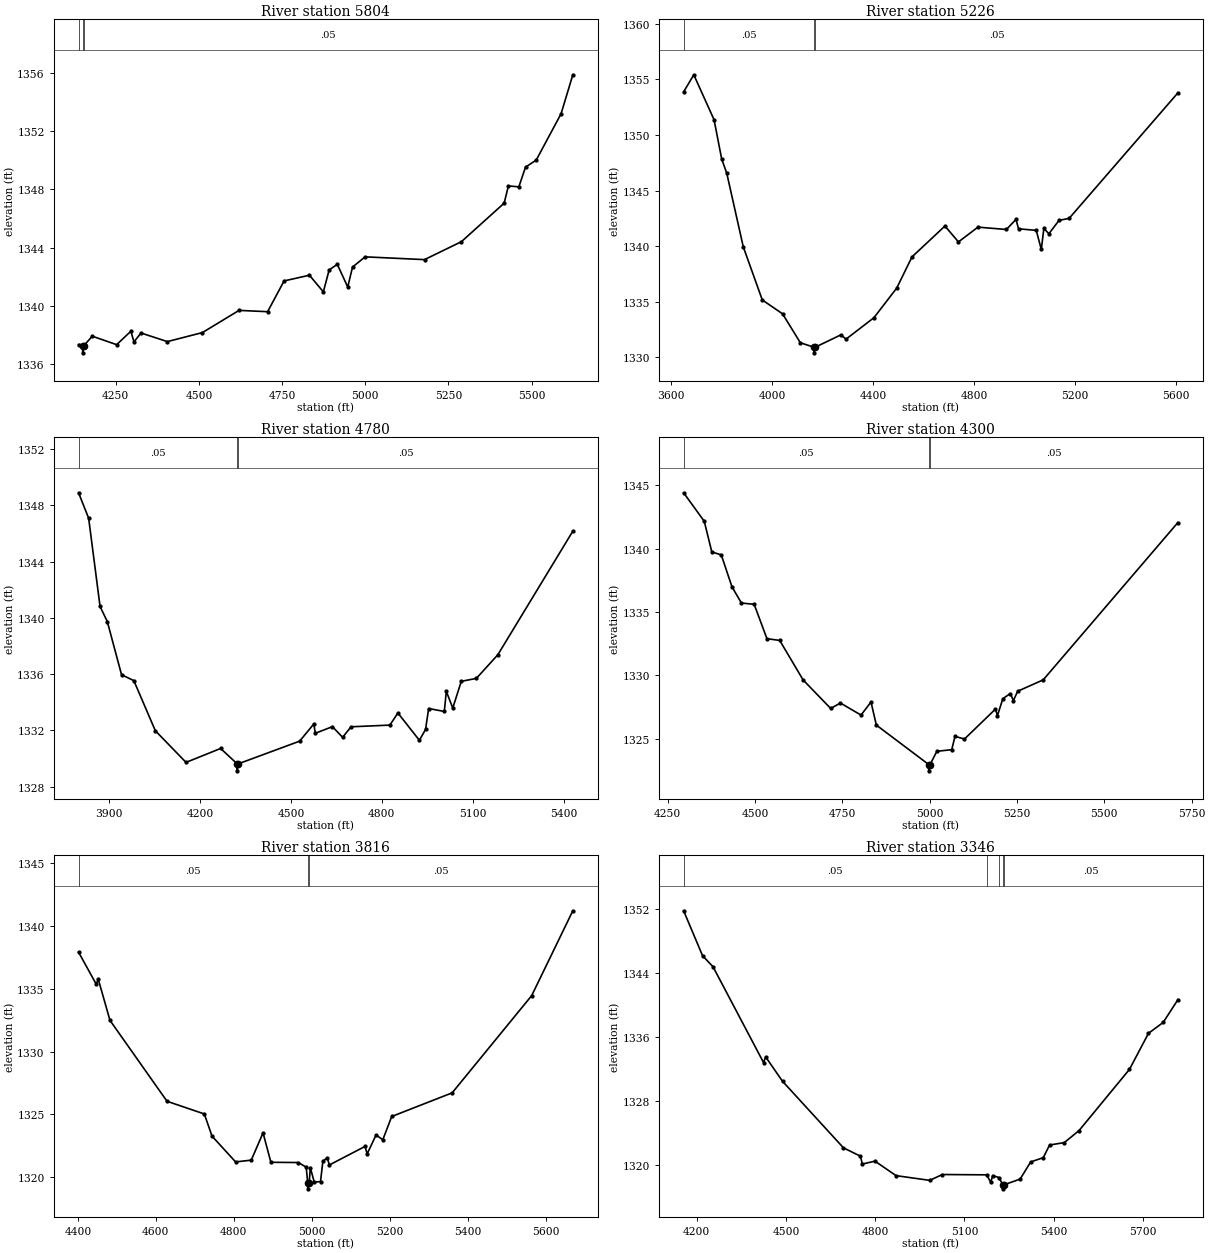
Type RM Length L Ch R = 1,5804,578,578,578
BEGIN DESCRIPTION:
Mapping XS 9981c7b6
END DESCRIPTION:
XS GIS Cut Line= 4
      2826729.26     10290487.69      2826414.58     10290292.37
      2825926.30     10290140.46      2825351.20     10289955.99
#Sta/Elev= 30
  4138.1 1337.36  4150.2 1337.29  4150.5 1336.79  4154.2 1337.29  4179.4 1337.93
  4252.6 1337.35  4295.3 1338.27  4304.6 1337.54  4325.8 1338.15  4405.0 1337.56
  4510.5 1338.18  4620.5 1339.70  4706.3 1339.61  4755.9 1341.72  4832.0 1342.11
  4873.9 1340.97  4891.3 1342.47  4915.8 1342.86  4947.2 1341.30  4961.6 1342.67
  4999.5 1343.37  5178.0 1343.18  5288.9 1344.41  5417.4 1347.05  5430.1 1348.23
  5461.6 1348.17  5481.6 1349.52  5513.7 1350.00  5588.5 1353.18  5623.8 1355.85
#Mann=3,-1,0
  4138.1    0.05       0  4150.2    0.03       0  4154.2    0.05       0
Bank Sta=4150.2,4154.2
Exp/Cntr=0.3,0.1

Type RM Length L Ch R = 1,5226,446,446,446
BEGIN DESCRIPTION:
LITTLE LLANO 034 7.0
END DESCRIPTION:
XS GIS Cut Line= 3
      2827505.72     10289553.11      2826162.00     10289696.00
      2825555.71     10289653.11
#Sta/Elev= 30
  3648.7 1353.88  3689.0 1355.42  3769.4 1351.37  3799.6 1347.84  3819.7 1346.56
  3885.1 1339.94  3960.5 1335.16  4040.9 1333.91  4111.3 1331.31  4165.8 1330.90
  4166.0 1330.40  4169.8 1330.90  4272.2 1332.02  4292.3 1331.63  4403.0 1333.56
  4493.5 1336.23  4553.8 1339.03  4684.5 1341.81  4738.1 1340.38  4815.3 1341.71
  4928.2 1341.50  4966.1 1342.41  4976.2 1341.56  5046.4 1341.42  5066.5 1339.70
  5076.5 1341.59  5096.6 1341.12  5136.7 1342.32  5176.8 1342.50  5607.8 1353.79
#Mann=3,-1,0
  3648.7    0.05       0  4165.8    0.04       0  4169.8    0.05       0
Bank Sta=4165.8,4169.8
Exp/Cntr=0.3,0.1

Type RM Length L Ch R = 1,4780,480,480,480
BEGIN DESCRIPTION:
LITTLE LLANO 034 6.0
END DESCRIPTION:
XS GIS Cut Line= 3
      2827305.67     10289453.11      2826120.50     10289260.00
      2825805.72     10289553.08
#Sta/Elev= 30
  3799.2 1348.89  3832.5 1347.08  3870.1 1340.81  3894.0 1339.74  3941.0 1335.96
  3981.6 1335.54  4052.5 1331.98  4153.8 1329.73  4267.9 1330.72  4322.4 1329.63
  4322.6 1329.13  4326.4 1329.63  4528.7 1331.24  4575.4 1332.46  4580.4 1331.80
  4636.9 1332.27  4670.5 1331.51  4698.3 1332.26  4826.4 1332.38  4852.9 1333.24
  4923.8 1331.30  4944.1 1332.07  4954.4 1333.56  5006.0 1333.35  5012.7 1334.78
  5033.9 1333.59  5062.0 1335.49  5111.8 1335.70  5182.7 1337.38  5430.1 1346.16
#Mann=3,-1,0
  3799.2    0.05       0  4322.4    0.03       0  4326.4    0.05       0
Bank Sta=4322.4,4326.4
Exp/Cntr=0.3,0.1

Type RM Length L Ch R = 1,4300,484,484,484
BEGIN DESCRIPTION:
LITTLE LLANO 034 5.0
END DESCRIPTION:
XS GIS Cut Line= 3
      2826855.71     10288453.09      2826259.25     10288828.00
      2825655.71     10289203.09
#Sta/Elev= 30
  4295.5 1344.41  4354.6 1342.16  4376.2 1339.74  4403.3 1339.51  4433.9 1336.99
  4461.0 1335.71  4497.5 1335.61  4534.0 1332.90  4570.6 1332.76  4637.7 1329.64
  4716.6 1327.39  4744.4 1327.82  4803.4 1326.87  4832.0 1327.90  4847.3 1326.08
  4997.2 1322.97  4997.4 1322.47  5001.2 1322.97  5020.5 1324.01  5063.1 1324.14
  5072.5 1325.19  5099.6 1324.98  5188.2 1327.34  5194.1 1326.83  5209.4 1328.16
  5230.7 1328.57  5239.7 1328.02  5251.9 1328.75  5325.1 1329.65  5710.6 1342.06
#Mann=3,-1,0
  4295.5    0.05       0  4997.2    0.03       0  5001.2    0.05       0
Bank Sta=4997.2,5001.2
Exp/Cntr=0.3,0.1

Type RM Length L Ch R = 1,3816,470,470,470
BEGIN DESCRIPTION:
LITTLE LLANO 034 4.0
END DESCRIPTION:
XS GIS Cut Line= 3
      2826655.71     10288353.11      2826061.25     10288419.00
      2825455.69     10288703.11
#Sta/Elev= 30
  4401.9 1337.90  4447.3 1335.35  4452.3 1335.76  4482.4 1332.48  4628.6 1326.05
  4724.3 1325.04  4744.0 1323.28  4804.4 1321.23  4844.6 1321.37  4874.8 1323.54
  4894.9 1321.20  4965.4 1321.18  4985.5 1320.81  4989.2 1319.59  4989.5 1319.09
  4993.2 1319.59  4996.0 1320.77  5006.1 1319.62  5022.1 1319.67  5028.2 1321.29
  5039.3 1321.55  5044.9 1320.99  5136.2 1322.46  5141.7 1321.87  5164.5 1323.37
  5181.8 1322.99  5204.6 1324.84  5359.6 1326.72  5563.5 1334.45  5668.9 1341.19
#Mann=3,-1,0
  4401.9    0.05       0  4989.2    0.03       0  4993.2    0.05       0
Bank Sta=4989.2,4993.2
Exp/Cntr=0.3,0.1

Type RM Length L Ch R = 1,3346,483,483,483
BEGIN DESCRIPTION:
LITTLE LLANO 034 3.0
END DESCRIPTION:
XS GIS Cut Line= 3
      2826605.66     10287403.13      2825996.75     10287988.00
      2825405.72     10288553.08
#Sta/Elev= 30
  4155.7 1351.74  4219.3 1346.13  4254.6 1344.74  4424.4 1332.77  4431.6 1333.47
  4488.2 1330.43  4693.3 1322.10  4749.9 1321.07  4756.8 1320.08  4799.2 1320.44
  4870.0 1318.63  4983.2 1318.04  5025.7 1318.77  5174.5 1318.73  5188.3 1317.81
  5195.2 1318.64  5216.9 1318.38  5228.7 1317.48  5229.0 1316.98  5232.7 1317.48
  5287.3 1318.20  5322.6 1320.34  5365.0 1320.88  5386.4 1322.46  5435.8 1322.76
  5485.5 1324.27  5655.0 1331.92  5718.8 1336.42  5768.2 1337.78  5817.7 1340.62
#Mann=5,-1,0
  4155.7    0.05       0  5174.5    0.12       0  5216.9    0.05       0
  5228.7    0.03       0  5232.7    0.05       0
Bank Sta=5228.7,5232.7
Exp/Cntr=0.3,0.1

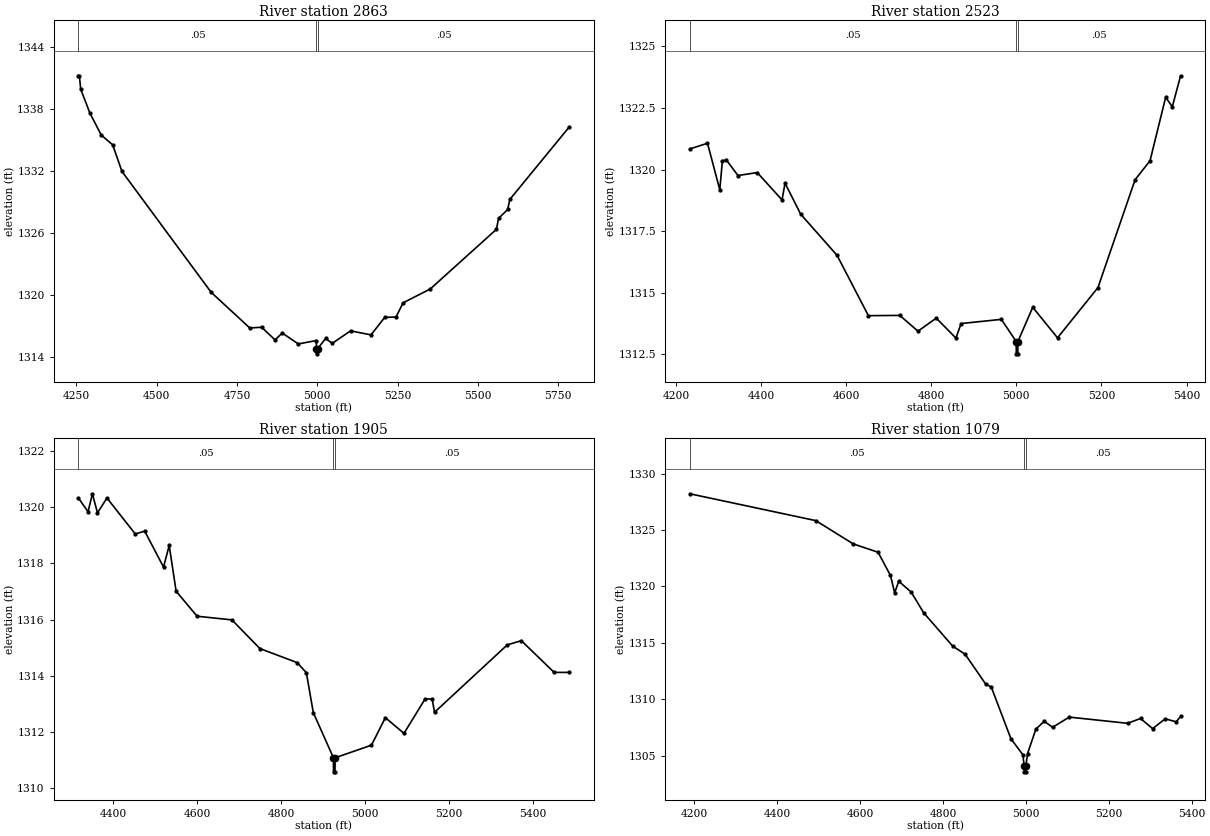
Type RM Length L Ch R = 1,2863,340,340,340
BEGIN DESCRIPTION:
LITTLE LLANO 034 2.0
END DESCRIPTION:
XS GIS Cut Line= 3
      2826255.66     10287203.13      2825669.75     10287661.00
      2825155.70     10288253.09
#Sta/Elev= 30
  4256.4 1341.25  4259.5 1341.25  4263.6 1339.95  4292.5 1337.61  4327.8 1335.49
  4363.1 1334.55  4392.0 1331.97  4669.7 1320.24  4790.0 1316.78  4827.0 1316.85
  4868.6 1315.62  4890.9 1316.29  4941.0 1315.23  4997.1 1315.56  4997.4 1314.77
  4997.7 1314.27  5001.4 1314.77  5025.9 1315.76  5046.7 1315.29  5103.7 1316.50
  5167.3 1316.11  5210.1 1317.81  5245.2 1317.84  5267.1 1319.22  5351.6 1320.56
  5557.7 1326.35  5564.3 1327.41  5592.8 1328.28  5599.4 1329.25  5784.1 1336.27
#Mann=3,-1,0
  4256.4    0.05       0  4997.4    0.03       0  5001.4    0.05       0
Bank Sta=4997.4,5001.4
Exp/Cntr=0.3,0.1

Type RM Length L Ch R = 1,2523,618,618,618
BEGIN DESCRIPTION:
Mapping XS d2bf7c00
END DESCRIPTION:
XS GIS Cut Line= 2
      2825806.93     10286787.62      2825210.43     10287774.56
#Sta/Elev= 30
  4232.7 1320.84  4274.2 1321.07  4303.1 1319.18  4309.2 1320.36  4318.6 1320.39
  4345.8 1319.76  4391.0 1319.88  4449.4 1318.77  4456.4 1319.45  4493.2 1318.19
  4578.6 1316.52  4652.3 1314.07  4726.1 1314.08  4768.8 1313.44  4811.7 1313.97
  4858.0 1313.16  4870.1 1313.75  4964.7 1313.92  4999.6 1313.02  4999.9 1312.52
  5003.4 1312.52  5003.6 1313.02  5038.5 1314.41  5096.7 1313.17  5191.7 1315.21
  5279.0 1319.59  5314.1 1320.36  5350.9 1322.94  5366.4 1322.55  5385.9 1323.81
#Mann=3,-1,0
  4232.7    0.05       0  4999.6    0.05       0  5003.6    0.05       0
Bank Sta=4999.6,5003.6
Exp/Cntr=0.3,0.1

Type RM Length L Ch R = 1,1905,826,826,826
BEGIN DESCRIPTION:
Mapping XS 9adde4b1
END DESCRIPTION:
XS GIS Cut Line= 3
      2825796.10     10286570.58      2825079.95     10286939.50
      2824917.20     10287264.99
#Sta/Elev= 30
  4316.8 1320.33  4339.8 1319.84  4350.2 1320.48  4362.3 1319.80  4384.8 1320.33
  4452.3 1319.05  4474.8 1319.15  4519.7 1317.87  4533.2 1318.64  4549.7 1317.01
  4599.7 1316.12  4682.7 1315.99  4749.2 1314.97  4837.9 1314.47  4860.1 1314.11
  4876.6 1312.69  4924.6 1311.08  4924.8 1310.58  4928.3 1310.58  4928.6 1311.08
  5015.3 1311.53  5048.3 1312.51  5092.7 1311.95  5143.2 1313.18  5159.9 1313.17
  5165.5 1312.70  5338.8 1315.10  5372.4 1315.25  5450.6 1314.12  5486.3 1314.12
#Mann=3,-1,0
  4316.8    0.05       0  4924.6    0.05       0  4928.6    0.05       0
Bank Sta=4924.6,4928.6
Exp/Cntr=0.3,0.1

Type RM Length L Ch R = 1,1079,0,0,0
BEGIN DESCRIPTION:
LITTLE LLANO 034 1.0
END DESCRIPTION:
XS GIS Cut Line= 3
      2825839.51     10286223.36      2825115.15     10286249.11
      2824658.70     10286299.10
#Sta/Elev= 30
  4189.2 1328.21  4493.2 1325.83  4583.3 1323.77  4643.3 1323.03  4673.3 1320.97
  4683.3 1319.43  4693.3 1320.46  4723.4 1319.49  4753.4 1317.66  4823.4 1314.71
  4853.4 1313.99  4903.5 1311.32  4916.3 1311.10  4963.8 1306.51  4992.8 1305.08
  4995.8 1304.07  4996.1 1303.57  4999.6 1303.57  4999.8 1304.07  5004.0 1305.19
  5024.1 1307.36  5044.3 1308.05  5064.4 1307.52  5104.6 1308.42  5245.5 1307.87
  5276.5 1308.30  5305.8 1307.40  5336.0 1308.27  5362.6 1308.00  5373.2 1308.48
#Mann=3,-1,0
  4189.2    0.05       0  4995.8    0.05       0  4999.8    0.05       0
Bank Sta=4995.8,4999.8
Exp/Cntr=0.3,0.1

Chan Stop Cuts=-1