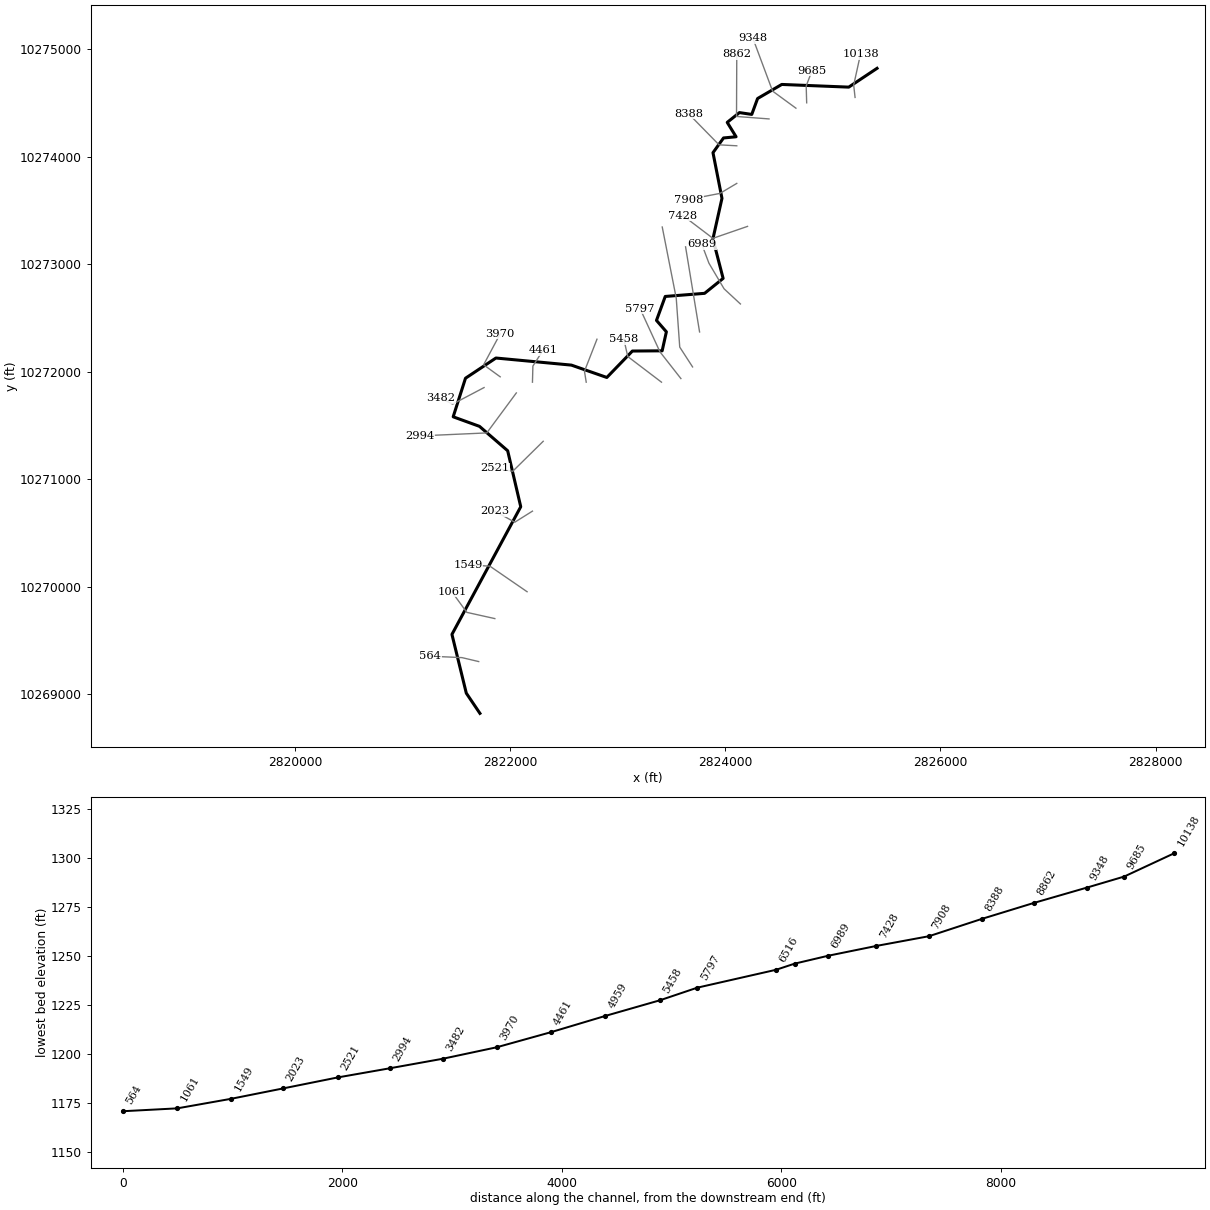
--- LITTLE LLANO 040.prj (project) ---

Proj Title=LITTLE LLANO 040 Base Level Engineering
Current Plan=p01
Default Exp/Contr=0.3,0.1
English Units
Geom File=g01
Flow File=f01
Plan File=p01
BEGIN DESCRIPTION:
LITTLE LLANO 040
END DESCRIPTION:

--- LITTLE LLANO 040.p01 (plan) ---

Plan Title=Multiple Run
Short Identifier=Multiple
Geom File=g01
Flow File=f01
Subcritical Flow
K Sum by GR= 0
Std Step Tol= 0.01
Critical Tol= 0.01
Num of Std Step Trials= 20
Max Error Tol= 0.3
Flow Tol Ratio= 0.001
Split Flow NTrial= 30
Split Flow Tol= 0.02
Split Flow Ratio= 0.02
Log Output Level= 0
Friction Slope Method= 1
Unsteady Friction Slope Method= 2
Unsteady Bridges Friction Slope Method= 1
Parabolic Critical Depth
Global Vel Dist=  1 , 1 , 1
Global Log Level= 0
CheckData=True
Encroach Param= -1, 0, 0, 0
BEGIN DESCRIPTION:
Multiple Run
END DESCRIPTION:

--- LITTLE LLANO 040.f01 (steady flow) ---

Flow Title=Multiple
Number of Profiles=7
Profile Names=10-year,25-year,50-year,1pct_min,100-year,1pct_plu,500-year
River Rch & RM= LITTLE LLANO 040,Reach-1,10138
      43      72     106      53     160     482     395
River Rch & RM= LITTLE LLANO 040,Reach-1,3482
      68     127     197     102     308     929     807
River Rch & RM= LITTLE LLANO 040,Reach-1,2521
      75     144     226     118     355    1072     942
Boundary for River Rch & Prof#=LITTLE LLANO 040,Reach-1,1
Up Type=0
Dn Type=3
Dn Slope=0.005
Boundary for River Rch & Prof#=LITTLE LLANO 040,Reach-1,2
Up Type=0
Dn Type=3
Dn Slope=0.005
Boundary for River Rch & Prof#=LITTLE LLANO 040,Reach-1,3
Up Type=0
Dn Type=3
Dn Slope=0.005
Boundary for River Rch & Prof#=LITTLE LLANO 040,Reach-1,4
Up Type=0
Dn Type=3
Dn Slope=0.005
Boundary for River Rch & Prof#=LITTLE LLANO 040,Reach-1,5
Up Type=0
Dn Type=3
Dn Slope=0.005
Boundary for River Rch & Prof#=LITTLE LLANO 040,Reach-1,6
Up Type=0
Dn Type=3
Dn Slope=0.005
Boundary for River Rch & Prof#=LITTLE LLANO 040,Reach-1,7
Up Type=0
Dn Type=3
Dn Slope=0.005

--- LITTLE LLANO 040.g01 (geometry) ---

Geom Title=Existing Conditions

River Reach=LITTLE LLANO 040,Reach-1
Reach XY= 30
      2825410.00     10274824.00      2825147.00     10274649.00
      2824524.25     10274674.00      2824299.25     10274543.00
      2824245.00     10274395.00      2824130.50     10274412.00
      2824016.75     10274321.00      2824099.25     10274187.00
      2823982.50     10274176.00      2823884.50     10274039.00
      2823968.00     10273614.00      2823883.75     10273236.00
      2823978.75     10272869.00      2823806.50     10272730.00
      2823440.50     10272701.00      2823359.00     10272478.00
      2823451.00     10272372.00      2823411.75     10272195.00
      2823135.00     10272193.00      2822897.25     10271947.00
      2822568.00     10272062.00      2821866.00     10272128.00
      2821583.00     10271940.00      2821468.50     10271581.00
      2821713.25     10271492.00      2821975.25     10271265.00
      2822096.75     10270744.00      2821457.00     10269556.00
      2821590.50     10269009.00      2821717.25     10268821.00

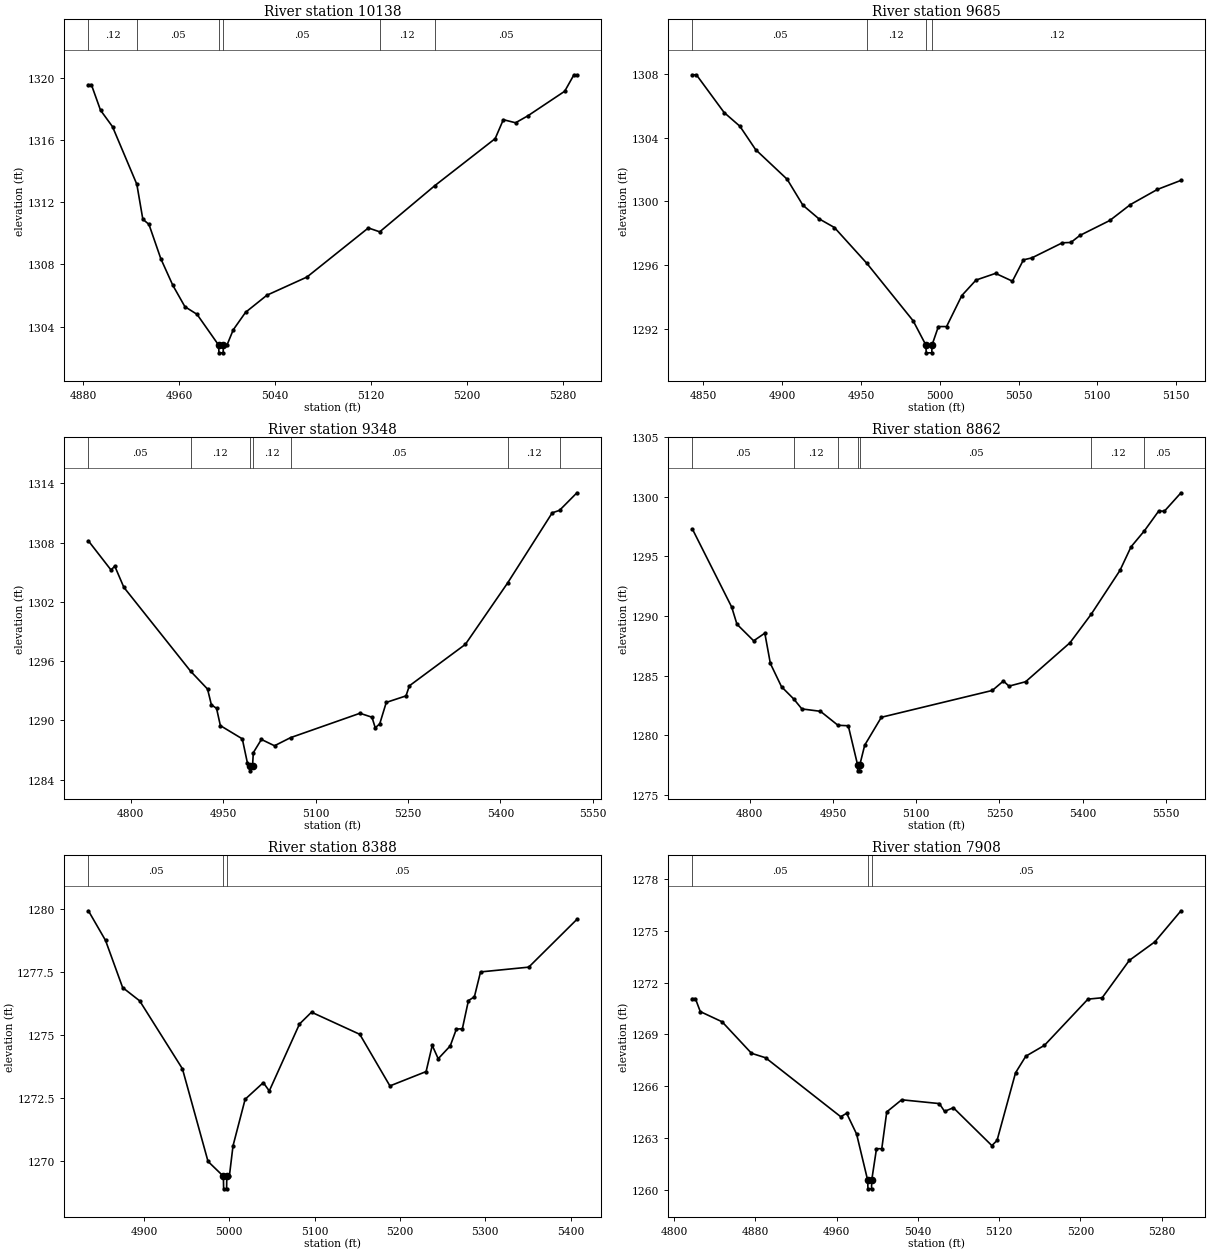
Type RM Length L Ch R = 1,10138,453,453,453
BEGIN DESCRIPTION:
LITTLE LLANO 040 21.0
END DESCRIPTION:
XS GIS Cut Line= 3
      2825205.69     10274553.10      2825193.00     10274668.00
      2825255.68     10274953.09
#Sta/Elev= 30
  4884.4 1319.57  4886.9 1319.57  4894.5 1317.93  4904.5 1316.87  4924.8 1313.16
  4929.8 1310.91  4934.9 1310.58  4944.8 1308.37  4954.8 1306.66  4964.9 1305.28
  4975.0 1304.79  4993.0 1302.81  4993.3 1302.31  4996.8 1302.31  4997.0 1302.81
  5000.0 1302.81  5005.2 1303.79  5015.5 1304.92  5033.3 1306.02  5066.7 1307.19
  5117.9 1310.35  5127.4 1310.10  5173.3 1313.07  5223.7 1316.10  5230.5 1317.32
  5240.7 1317.12  5251.0 1317.57  5281.7 1319.15  5289.4 1320.21  5291.9 1320.21
#Mann=6,-1,0
  4884.4    0.12       0  4924.8    0.05       0  4993.0    0.05       0
  4997.0    0.05       0  5127.4    0.12       0  5173.3    0.05       0
Bank Sta=4993,4997
Exp/Cntr=0.3,0.1

Type RM Length L Ch R = 1,9685,337,337,337
BEGIN DESCRIPTION:
LITTLE LLANO 040 20.0
END DESCRIPTION:
XS GIS Cut Line= 3
      2824755.69     10274503.06      2824751.25     10274660.00
      2824805.68     10274803.10
#Sta/Elev= 30
  4843.0 1307.95  4845.5 1307.95  4863.1 1305.58  4873.1 1304.72  4883.1 1303.25
  4903.1 1301.39  4913.1 1299.76  4923.1 1298.92  4933.1 1298.36  4953.7 1296.11
  4983.1 1292.50  4991.1 1290.99  4991.4 1290.49  4994.9 1290.49  4995.1 1290.99
  4999.1 1292.14  5004.3 1292.14  5014.0 1294.09  5023.0 1295.06  5035.4 1295.48
  5046.1 1294.99  5053.1 1296.33  5058.4 1296.45  5077.8 1297.40  5083.2 1297.42
  5088.9 1297.86  5107.9 1298.80  5121.0 1299.80  5138.1 1300.75  5153.1 1301.32
#Mann=4,-1,0
  4843.0    0.05       0  4953.7    0.12       0  4991.1    0.07       0
  4995.1    0.12       0
Bank Sta=4991.1,4995.1
Exp/Cntr=0.3,0.1

Type RM Length L Ch R = 1,9348,486,486,486
BEGIN DESCRIPTION:
LITTLE LLANO 040 19.0
END DESCRIPTION:
XS GIS Cut Line= 3
      2824655.69     10274453.11      2824438.75     10274612.00
      2824255.69     10275103.09
#Sta/Elev= 30
  4731.1 1308.19  4767.8 1305.24  4773.9 1305.63  4788.6 1303.49  4897.0 1294.99
  4924.5 1293.18  4930.7 1291.59  4939.1 1291.23  4945.3 1289.48  4980.9 1288.14
  4989.3 1285.67  4993.5 1285.40  4993.8 1284.90  4997.5 1285.40  4998.8 1286.74
  5011.9 1288.08  5033.2 1287.44  5059.2 1288.26  5171.9 1290.73  5191.4 1290.33
  5196.7 1289.26  5204.0 1289.66  5214.6 1291.83  5246.6 1292.49  5252.1 1293.51
  5343.0 1297.71  5411.4 1303.91  5484.0 1311.03  5495.8 1311.28  5524.1 1313.06
#Mann=7,-1,0
  4731.1    0.05       0  4897.0    0.12       0  4993.5    0.07       0
  4997.5    0.12       0  5059.2    0.05       0  5411.4    0.12       0
  5495.8    0.05       0
Bank Sta=4993.5,4997.5
Exp/Cntr=0.3,0.1

Type RM Length L Ch R = 1,8862,474,474,474
BEGIN DESCRIPTION:
LITTLE LLANO 040 18.0
END DESCRIPTION:
XS GIS Cut Line= 3
      2824405.69     10274353.11      2824103.25     10274376.00
      2824105.68     10274953.09
#Sta/Elev= 30
  4696.7 1297.29  4767.4 1290.76  4776.9 1289.32  4807.0 1287.93  4827.1 1288.57
  4837.1 1286.03  4857.2 1284.08  4879.1 1283.06  4893.9 1282.22  4927.4 1282.02
  4958.9 1280.85  4977.5 1280.81  4994.3 1277.53  4994.5 1277.03  4998.0 1277.03
  4998.3 1277.53  5007.1 1279.18  5037.1 1281.52  5237.1 1283.77  5257.1 1284.56
  5267.1 1284.13  5297.1 1284.50  5377.1 1287.77  5415.3 1290.16  5467.1 1293.83
  5487.1 1295.81  5511.3 1297.16  5537.1 1298.82  5547.1 1298.79  5577.1 1300.34
#Mann=7,-1,0
  4696.7    0.05       0  4879.1    0.12       0  4958.9    0.05       0
  4994.3    0.05       0  4998.3    0.05       0  5415.3    0.12       0
  5511.3    0.05       0
Bank Sta=4994.3,4998.3
Exp/Cntr=0.3,0.1

Type RM Length L Ch R = 1,8388,480,480,480
BEGIN DESCRIPTION:
LITTLE LLANO 040 17.0
END DESCRIPTION:
XS GIS Cut Line= 3
      2824105.71     10274103.11      2823940.75     10274112.00
      2823655.71     10274403.08
#Sta/Elev= 30
  4834.8 1279.93  4854.9 1278.75  4874.9 1276.88  4894.9 1276.35  4945.0 1273.65
  4975.0 1269.97  4993.0 1269.38  4993.3 1268.88  4996.8 1268.88  4997.0 1269.38
  5000.0 1269.38  5004.3 1270.59  5018.5 1272.44  5039.8 1273.10  5046.8 1272.77
  5082.2 1275.43  5096.3 1275.90  5152.9 1275.02  5188.2 1272.97  5230.6 1273.54
  5237.8 1274.58  5244.8 1274.05  5258.9 1274.56  5266.1 1275.23  5273.1 1275.24
  5280.2 1276.36  5287.2 1276.51  5294.4 1277.50  5350.9 1277.69  5407.4 1279.59
#Mann=3,-1,0
  4834.8    0.05       0  4993.0    0.03       0  4997.0    0.05       0
Bank Sta=4993,4997
Exp/Cntr=0.3,0.1

Type RM Length L Ch R = 1,7908,480,480,480
BEGIN DESCRIPTION:
LITTLE LLANO 040 16.0
END DESCRIPTION:
XS GIS Cut Line= 3
      2824105.64     10273753.09      2823949.25     10273660.00
      2823655.71     10273603.12
#Sta/Elev= 30
  4818.0 1271.07  4820.9 1271.07  4825.7 1270.32  4847.2 1269.73  4876.1 1267.91
  4890.0 1267.65  4964.0 1264.24  4969.8 1264.44  4979.6 1263.24  4990.5 1260.57
  4990.8 1260.07  4994.3 1260.07  4994.5 1260.57  4999.2 1262.39  5004.4 1262.39
  5009.3 1264.52  5024.0 1265.22  5061.1 1265.00  5066.2 1264.55  5074.9 1264.76
  5112.8 1262.57  5117.9 1262.87  5136.1 1266.78  5146.2 1267.74  5164.6 1268.37
  5207.4 1271.04  5221.4 1271.12  5248.1 1273.28  5273.2 1274.35  5299.0 1276.15
#Mann=3,-1,0
  4818.0    0.05       0  4990.5    0.05       0  4994.5    0.05       0
Bank Sta=4990.5,4994.5
Exp/Cntr=0.3,0.1

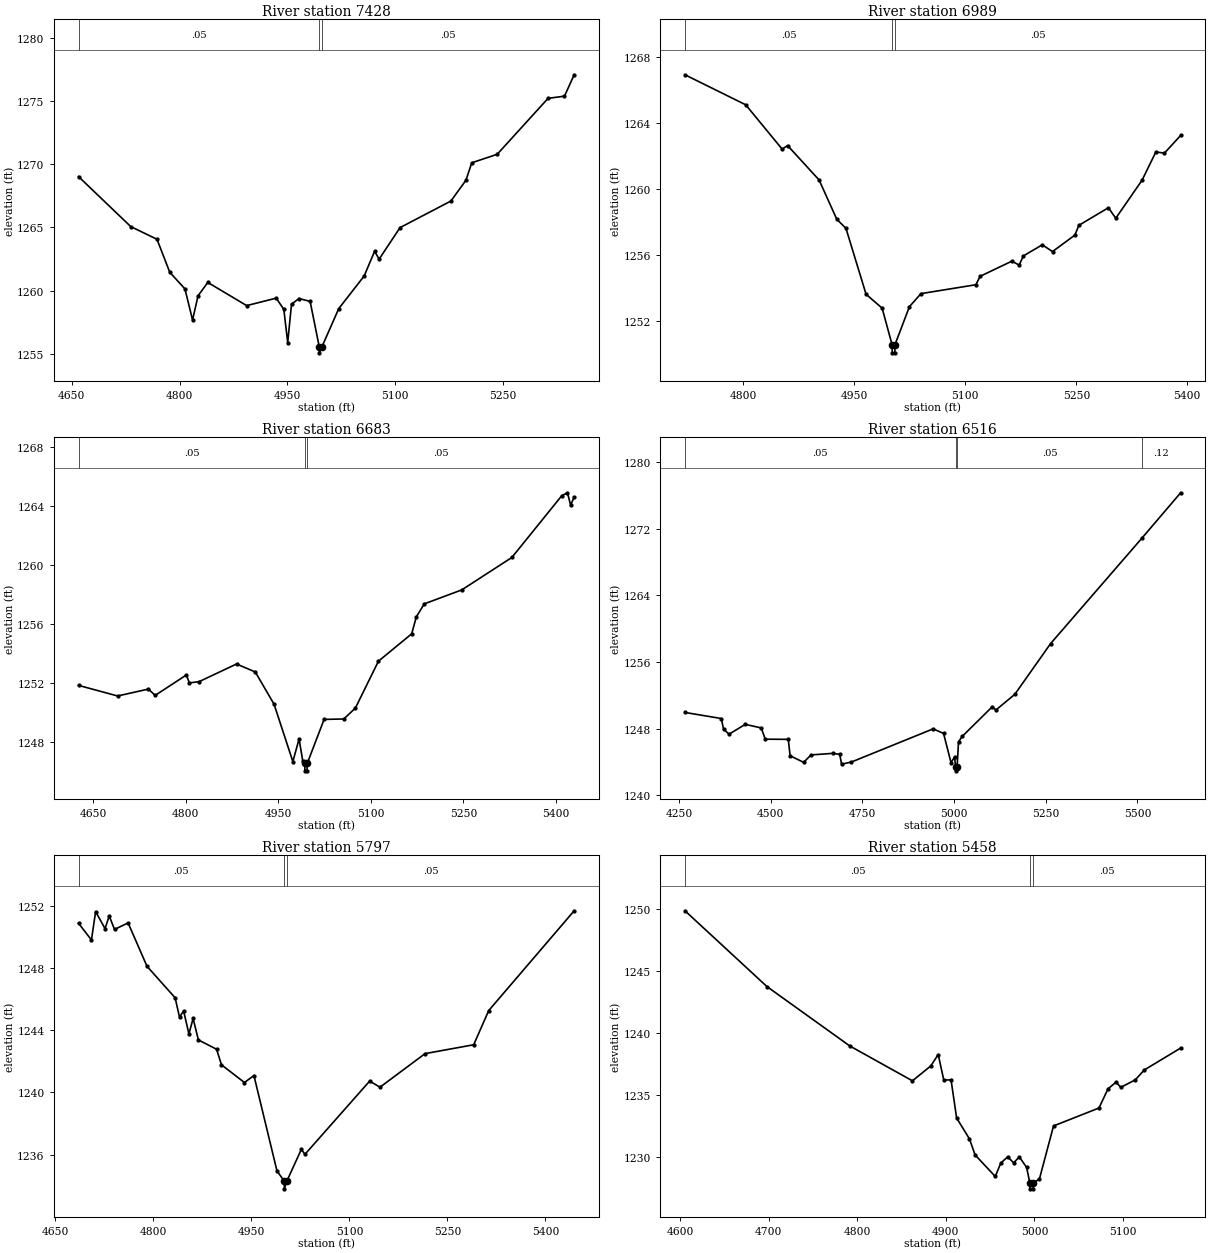
Type RM Length L Ch R = 1,7428,439,439,439
BEGIN DESCRIPTION:
LITTLE LLANO 040 15.0
END DESCRIPTION:
XS GIS Cut Line= 3
      2824205.71     10273353.12      2823883.75     10273242.00
      2823605.70     10273453.10
#Sta/Elev= 30
  4659.4 1269.02  4732.1 1265.07  4768.6 1264.07  4786.4 1261.46  4807.5 1260.15
  4818.1 1257.69  4825.7 1259.60  4839.3 1260.66  4893.4 1258.83  4934.5 1259.42
  4945.1 1258.53  4950.5 1255.91  4955.8 1258.94  4966.2 1259.39  4981.7 1259.16
  4994.3 1255.60  4994.6 1255.10  4998.3 1255.60  5021.5 1258.59  5056.9 1261.17
  5071.4 1263.12  5077.7 1262.50  5106.8 1264.99  5177.6 1267.09  5198.5 1268.73
  5206.6 1270.11  5242.0 1270.78  5312.8 1275.20  5335.6 1275.37  5349.1 1277.06
#Mann=3,-1,0
  4659.4    0.05       0  4994.3    0.03       0  4998.3    0.05       0
Bank Sta=4994.3,4998.3
Exp/Cntr=0.3,0.1

Type RM Length L Ch R = 1,6989,306,306,306
BEGIN DESCRIPTION:
Mapping XS 5735dfff
END DESCRIPTION:
XS GIS Cut Line= 4
      2824139.53     10272631.08      2823987.64     10272772.11
      2823846.58     10273010.83      2823781.47     10273184.48
#Sta/Elev= 30
  4721.0 1266.95  4803.1 1265.13  4852.4 1262.44  4859.7 1262.66  4902.3 1260.57
  4926.2 1258.19  4938.6 1257.64  4965.8 1253.64  4987.5 1252.80  5000.9 1250.59
  5001.2 1250.09  5004.7 1250.09  5004.9 1250.59  5024.4 1252.89  5040.0 1253.68
  5114.2 1254.22  5120.0 1254.73  5162.9 1255.65  5172.7 1255.41  5178.5 1255.97
  5204.0 1256.64  5217.8 1256.23  5248.1 1257.23  5253.4 1257.82  5293.4 1258.89
  5303.3 1258.25  5338.9 1260.56  5357.5 1262.27  5369.1 1262.20  5391.0 1263.27
#Mann=3,-1,0
  4721.0    0.05       0  5000.9    0.03       0  5004.9    0.05       0
Bank Sta=5000.9,5004.9
Exp/Cntr=0.3,0.1

Type RM Length L Ch R = 1,6683,167,167,167
BEGIN DESCRIPTION:
Mapping XS 417a2d2d
END DESCRIPTION:
XS GIS Cut Line= 2
      2823759.78     10272370.64      2823629.57     10273162.71
#Sta/Elev= 30
  4626.7 1251.85  4690.0 1251.13  4740.0 1251.60  4750.8 1251.17  4801.2 1252.55
  4806.3 1252.02  4821.8 1252.10  4882.6 1253.30  4913.0 1252.76  4943.4 1250.57
  4973.8 1246.68  4983.9 1248.21  4990.0 1246.69  4993.1 1246.55  4993.3 1246.05
  4996.8 1246.05  4997.1 1246.55  5024.4 1249.54  5056.3 1249.57  5075.1 1250.31
  5112.4 1253.49  5166.3 1255.35  5173.7 1256.49  5186.6 1257.38  5247.4 1258.33
  5328.5 1260.53  5409.5 1264.73  5418.6 1264.92  5423.6 1264.08  5429.4 1264.63
#Mann=3,-1,0
  4626.7    0.05       0  4993.1    0.03       0  4997.1    0.05       0
Bank Sta=4993.1,4997.1
Exp/Cntr=0.3,0.1

Type RM Length L Ch R = 1,6516,719,719,719
BEGIN DESCRIPTION:
Mapping XS c16c0a35
END DESCRIPTION:
XS GIS Cut Line= 4
      2823694.68     10272045.11      2823575.32     10272229.58
      2823542.76     10272685.31      2823412.55     10273347.22
#Sta/Elev= 30
  4266.5 1249.96  4365.6 1249.23  4371.6 1247.95  4386.7 1247.35  4430.9 1248.53
  4474.4 1248.10  4485.3 1246.75  4548.1 1246.73  4553.1 1244.76  4590.0 1243.97
  4610.1 1244.86  4670.2 1245.05  4688.4 1244.93  4693.4 1243.75  4720.3 1244.01
  4943.1 1247.99  4971.4 1247.44  4991.8 1243.93  5001.3 1244.61  5004.4 1243.45
  5004.7 1242.95  5008.4 1243.45  5012.2 1246.43  5022.4 1247.09  5103.9 1250.63
  5114.3 1250.26  5165.6 1252.13  5263.3 1258.23  5512.1 1270.88  5617.7 1276.33
#Mann=4,-1,0
  4266.5    0.05       0  5004.4    0.03       0  5008.4    0.05       0
  5512.1    0.12       0
Bank Sta=5004.4,5008.4
Exp/Cntr=0.3,0.1

Type RM Length L Ch R = 1,5797,339,339,339
BEGIN DESCRIPTION:
Mapping XS 1492f16c
END DESCRIPTION:
XS GIS Cut Line= 3
      2823586.14     10271936.64      2823390.85     10272186.18
      2823206.39     10272587.66
#Sta/Elev= 30
  4685.3 1250.89  4705.1 1249.81  4711.5 1251.64  4725.9 1250.54  4732.3 1251.36
  4740.4 1250.49  4761.2 1250.91  4790.1 1248.12  4833.2 1246.09  4839.9 1244.85
  4846.2 1245.24  4854.3 1243.77  4860.7 1244.76  4868.8 1243.38  4896.7 1242.78
  4904.1 1241.78  4939.3 1240.64  4953.8 1241.09  4989.1 1234.95  5000.2 1234.30
  5000.4 1233.80  5004.2 1234.30  5026.4 1236.34  5031.9 1236.02  5130.9 1240.73
  5146.8 1240.34  5215.8 1242.50  5290.2 1243.07  5313.2 1245.27  5444.0 1251.69
#Mann=3,-1,0
  4685.3    0.05       0  5000.2    0.05       0  5004.2    0.05       0
Bank Sta=5000.2,5004.2
Exp/Cntr=0.3,0.1

Type RM Length L Ch R = 1,5458,499,499,499
BEGIN DESCRIPTION:
LITTLE LLANO 040 11.0
END DESCRIPTION:
XS GIS Cut Line= 3
      2823405.69     10271903.11      2823091.75     10272142.00
      2823055.68     10272303.11
#Sta/Elev= 30
  4605.5 1249.89  4698.0 1243.76  4791.6 1238.95  4862.3 1236.13  4883.1 1237.34
  4891.4 1238.26  4897.7 1236.19  4905.9 1236.21  4912.2 1233.12  4926.7 1231.43
  4933.0 1230.14  4955.8 1228.39  4962.1 1229.48  4969.9 1229.98  4976.6 1229.49
  4982.9 1229.98  4991.2 1229.13  4994.8 1227.89  4995.0 1227.39  4998.5 1227.39
  4998.8 1227.89  5005.6 1228.17  5021.6 1232.48  5072.9 1233.93  5083.1 1235.48
  5092.3 1236.03  5097.5 1235.60  5113.9 1236.21  5124.1 1237.01  5165.1 1238.78
#Mann=3,-1,0
  4605.5    0.05       0  4994.8    0.05       0  4998.8    0.05       0
Bank Sta=4994.8,4998.8
Exp/Cntr=0.3,0.1

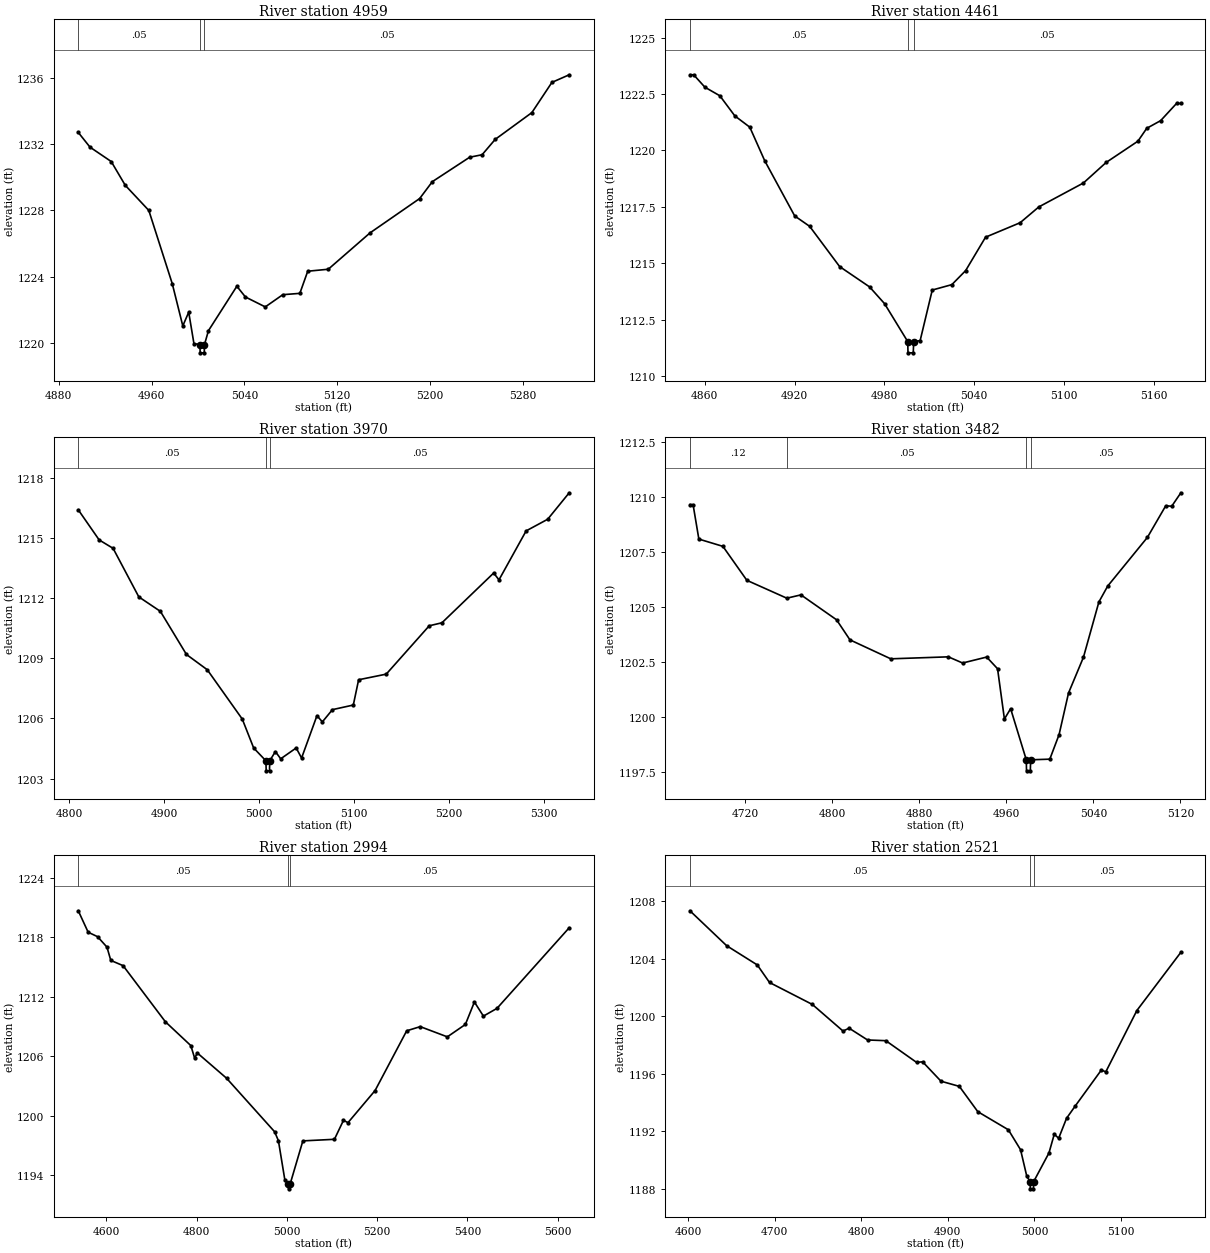
Type RM Length L Ch R = 1,4959,498,498,498
BEGIN DESCRIPTION:
LITTLE LLANO 040 10.0
END DESCRIPTION:
XS GIS Cut Line= 3
      2822705.68     10271903.12      2822689.25     10272005.00
      2822805.67     10272303.07
#Sta/Elev= 30
  4896.8 1232.72  4906.9 1231.83  4925.2 1230.96  4937.3 1229.52  4957.6 1228.00
  4977.8 1223.57  4986.9 1221.01  4992.0 1221.84  4996.5 1219.94  5001.6 1219.88
  5001.9 1219.38  5005.4 1219.38  5005.6 1219.88  5009.0 1220.72  5033.5 1223.41
  5040.9 1222.76  5058.0 1222.16  5073.1 1222.90  5087.8 1222.98  5094.6 1224.32
  5112.3 1224.44  5148.3 1226.64  5191.1 1228.72  5202.0 1229.74  5234.2 1231.22
  5244.9 1231.37  5256.2 1232.30  5287.8 1233.92  5305.1 1235.75  5320.0 1236.21
#Mann=3,-1,0
  4896.8    0.05       0  5001.6    0.05       0  5005.6    0.05       0
Bank Sta=5001.6,5005.6
Exp/Cntr=0.3,0.1

Type RM Length L Ch R = 1,4461,491,491,491
BEGIN DESCRIPTION:
LITTLE LLANO 040 9.0
END DESCRIPTION:
XS GIS Cut Line= 3
      2822205.69     10271903.16      2822209.75     10272053.00
      2822305.66     10272203.07
#Sta/Elev= 30
  4850.1 1223.35  4852.6 1223.35  4860.1 1222.80  4870.1 1222.42  4880.1 1221.53
  4890.1 1221.03  4900.1 1219.54  4920.1 1217.10  4930.1 1216.64  4950.1 1214.86
  4970.1 1213.96  4980.1 1213.22  4995.6 1211.54  4995.8 1211.04  4999.3 1211.04
  4999.6 1211.54  5003.9 1211.58  5012.0 1213.82  5025.1 1214.06  5034.3 1214.68
  5047.6 1216.16  5070.7 1216.80  5083.2 1217.50  5113.0 1218.56  5128.2 1219.47
  5149.4 1220.41  5155.3 1220.98  5164.6 1221.32  5175.2 1222.08  5178.1 1222.08
#Mann=3,-1,0
  4850.1    0.05       0  4995.6    0.05       0  4999.6    0.05       0
Bank Sta=4995.6,4999.6
Exp/Cntr=0.3,0.1

Type RM Length L Ch R = 1,3970,488,488,488
BEGIN DESCRIPTION:
LITTLE LLANO 040 8.0
END DESCRIPTION:
XS GIS Cut Line= 3
      2821905.68     10271953.11      2821751.50     10272065.00
      2821905.70     10272353.13
#Sta/Elev= 30
  4809.5 1216.40  4831.5 1214.90  4846.2 1214.48  4873.3 1212.06  4896.0 1211.34
  4923.5 1209.19  4945.4 1208.43  4982.3 1205.97  4994.3 1204.53  5007.2 1203.89
  5007.5 1203.39  5011.0 1203.39  5011.2 1203.89  5017.2 1204.35  5022.8 1203.99
  5039.1 1204.53  5044.8 1204.03  5061.0 1206.14  5066.7 1205.83  5077.3 1206.44
  5099.3 1206.67  5104.9 1207.93  5134.0 1208.21  5179.3 1210.62  5192.7 1210.77
  5247.2 1213.25  5252.8 1212.91  5281.4 1215.35  5304.1 1215.93  5326.8 1217.25
#Mann=3,-1,0
  4809.5    0.05       0  5007.2    0.03       0  5011.2    0.05       0
Bank Sta=5007.2,5011.2
Exp/Cntr=0.3,0.1

Type RM Length L Ch R = 1,3482,488,488,488
BEGIN DESCRIPTION:
LITTLE LLANO 040 7.0
END DESCRIPTION:
XS GIS Cut Line= 3
      2821755.72     10271853.13      2821463.25     10271699.00
      2821355.69     10271753.11
#Sta/Elev= 30
  4669.4 1209.64  4672.3 1209.64  4677.6 1208.08  4699.7 1207.75  4721.7 1206.21
  4758.4 1205.40  4771.4 1205.55  4804.1 1204.42  4816.4 1203.51  4853.9 1202.65
  4906.8 1202.74  4919.9 1202.46  4942.0 1202.73  4952.0 1202.20  4958.3 1199.92
  4964.0 1200.39  4978.4 1198.07  4978.6 1197.57  4982.1 1197.57  4982.4 1198.07
  5000.0 1198.10  5008.5 1199.21  5017.2 1201.10  5030.9 1202.72  5045.1 1205.23
  5053.2 1205.95  5089.7 1208.16  5106.5 1209.59  5112.0 1209.57  5120.4 1210.18
#Mann=4,-1,0
  4669.4    0.12       0  4758.4    0.05       0  4978.4    0.03       0
  4982.4    0.05       0
Bank Sta=4978.4,4982.4
Exp/Cntr=0.3,0.1

Type RM Length L Ch R = 1,2994,473,473,473
BEGIN DESCRIPTION:
LITTLE LLANO 040 6.0
END DESCRIPTION:
XS GIS Cut Line= 3
      2822055.68     10271803.10      2821781.00     10271431.00
      2821155.72     10271403.11
#Sta/Elev= 30
  4537.5 1220.66  4559.4 1218.50  4580.3 1218.05  4601.1 1217.00  4609.6 1215.66
  4636.9 1215.13  4730.6 1209.48  4787.0 1207.08  4795.4 1205.83  4801.6 1206.33
  4866.3 1203.79  4972.8 1198.40  4981.2 1197.50  4995.6 1193.51  5003.3 1193.15
  5003.6 1192.65  5007.3 1193.15  5035.4 1197.48  5105.4 1197.64  5125.4 1199.55
  5135.5 1199.32  5195.5 1202.55  5265.6 1208.57  5295.6 1208.99  5355.7 1207.96
  5395.7 1209.21  5415.7 1211.47  5435.7 1210.05  5465.8 1210.83  5625.9 1218.95
#Mann=3,-1,0
  4537.5    0.05       0  5003.3    0.03       0  5007.3    0.05       0
Bank Sta=5003.3,5007.3
Exp/Cntr=0.3,0.1

Type RM Length L Ch R = 1,2521,498,498,498
BEGIN DESCRIPTION:
LITTLE LLANO 040 5.0
END DESCRIPTION:
XS GIS Cut Line= 3
      2822305.69     10271353.12      2822022.25     10271074.00
      2821855.68     10271103.11
#Sta/Elev= 30
  4602.2 1207.34  4644.6 1204.91  4680.0 1203.57  4694.1 1202.35  4743.6 1200.82
  4779.0 1198.97  4786.0 1199.17  4807.3 1198.35  4828.4 1198.30  4863.9 1196.79
  4870.9 1196.83  4892.1 1195.48  4913.3 1195.12  4934.6 1193.36  4969.9 1192.10
  4984.0 1190.71  4991.2 1188.86  4995.1 1188.49  4995.3 1187.99  4998.8 1187.99
  4999.1 1188.49  5016.8 1190.49  5022.9 1191.79  5028.0 1191.51  5037.1 1192.90
  5047.3 1193.77  5077.3 1196.26  5082.4 1196.13  5118.3 1200.40  5169.1 1204.45
#Mann=3,-1,0
  4602.2    0.05       0  4995.1    0.05       0  4999.1    0.05       0
Bank Sta=4995.1,4999.1
Exp/Cntr=0.3,0.1

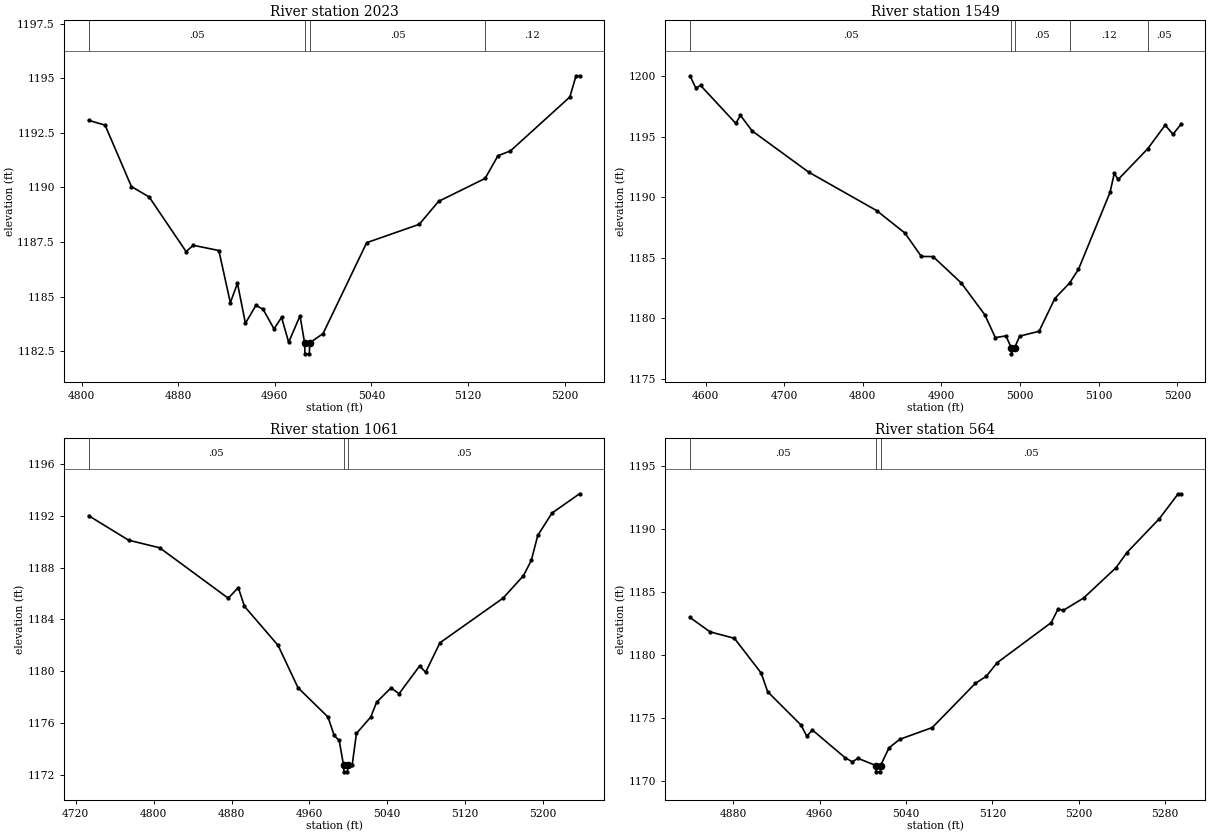
Type RM Length L Ch R = 1,2023,474,474,474
BEGIN DESCRIPTION:
LITTLE LLANO 040 4.0
END DESCRIPTION:
XS GIS Cut Line= 3
      2822205.69     10270703.12      2822041.25     10270600.00
      2821855.67     10270703.12
#Sta/Elev= 30
  4805.9 1193.07  4819.5 1192.85  4841.3 1190.04  4856.0 1189.56  4886.6 1187.06
  4892.5 1187.35  4913.7 1187.11  4923.2 1184.72  4929.1 1185.61  4935.7 1183.78
  4944.4 1184.60  4950.3 1184.42  4959.4 1183.52  4965.6 1184.05  4971.5 1182.91
  4980.9 1184.12  4984.7 1182.88  4985.0 1182.38  4988.6 1182.38  4988.9 1182.88
  5000.0 1183.31  5036.1 1187.47  5079.6 1188.31  5095.6 1189.36  5134.1 1190.41
  5144.8 1191.45  5155.1 1191.67  5204.3 1194.14  5209.4 1195.11  5212.3 1195.11
#Mann=4,-1,0
  4805.9    0.05       0  4984.7    0.03       0  4988.9    0.05       0
  5134.1    0.12       0
Bank Sta=4984.7,4988.9
Exp/Cntr=0.3,0.1

Type RM Length L Ch R = 1,1549,488,488,488
BEGIN DESCRIPTION:
LITTLE LLANO 040 3.0
END DESCRIPTION:
XS GIS Cut Line= 3
      2822155.66     10269953.13      2821809.75     10270191.00
      2821605.71     10270203.11
#Sta/Elev= 30
  4580.2 1200.01  4587.6 1199.00  4593.7 1199.21  4638.4 1196.09  4644.4 1196.74
  4659.3 1195.46  4731.0 1192.07  4817.6 1188.89  4853.5 1187.04  4874.4 1185.11
  4889.3 1185.10  4925.2 1182.92  4955.0 1180.31  4968.5 1178.42  4982.0 1178.56
  4988.7 1177.58  4989.0 1177.08  4993.0 1177.58  4999.4 1178.54  5024.1 1178.94
  5044.1 1181.64  5063.0 1182.93  5074.2 1184.05  5114.3 1190.39  5119.7 1191.96
  5124.7 1191.46  5162.2 1193.99  5184.4 1195.94  5194.4 1195.19  5204.4 1196.00
#Mann=5,-1,0
  4580.2    0.05       0  4988.7    0.03       0  4993.0    0.05       0
  5063.0    0.12       0  5162.2    0.05       0
Bank Sta=4988.7,4993
Exp/Cntr=0.3,0.1

Type RM Length L Ch R = 1,1061,497,497,497
BEGIN DESCRIPTION:
LITTLE LLANO 040 2.0
END DESCRIPTION:
XS GIS Cut Line= 3
      2821855.69     10269703.11      2821595.25     10269761.00
      2821455.66     10269953.15
#Sta/Elev= 30
  4733.2 1192.00  4774.2 1190.11  4806.2 1189.52  4876.6 1185.63  4886.9 1186.45
  4893.3 1185.00  4927.8 1181.99  4948.3 1178.72  4979.1 1176.46  4985.4 1175.04
  4990.6 1174.65  4995.1 1172.73  4995.4 1172.23  4999.1 1172.23  4999.4 1172.73
  5003.9 1172.73  5008.3 1175.19  5023.0 1176.46  5029.1 1177.61  5043.8 1178.71
  5052.1 1178.26  5073.2 1180.40  5079.4 1179.92  5094.1 1182.19  5159.0 1185.64
  5179.9 1187.37  5188.0 1188.56  5194.6 1190.48  5209.2 1192.20  5237.5 1193.69
#Mann=3,-1,0
  4733.2    0.05       0  4995.1    0.03       0  4999.4    0.05       0
Bank Sta=4995.1,4999.4
Exp/Cntr=0.3,0.1

Type RM Length L Ch R = 1,564,0,0,0
BEGIN DESCRIPTION:
LITTLE LLANO 040 1.0
END DESCRIPTION:
XS GIS Cut Line= 3
      2821705.69     10269303.11      2821550.00     10269340.00
      2821255.69     10269353.11
#Sta/Elev= 30
  4840.0 1182.99  4858.6 1181.85  4881.1 1181.34  4905.9 1178.59  4911.9 1177.11
  4942.8 1174.47  4948.2 1173.58  4953.3 1174.08  4983.9 1171.86  4990.4 1171.56
  4995.6 1171.83  5012.2 1171.26  5012.4 1170.76  5016.2 1170.76  5016.5 1171.26
  5024.3 1172.66  5034.3 1173.34  5064.4 1174.27  5104.4 1177.78  5114.4 1178.33
  5124.4 1179.40  5174.5 1182.58  5180.9 1183.66  5185.9 1183.56  5204.5 1184.53
  5234.5 1186.93  5244.6 1188.13  5274.6 1190.81  5292.1 1192.79  5294.6 1192.79
#Mann=3,-1,0
  4840.0    0.05       0  5012.2    0.03       0  5016.5    0.05       0
Bank Sta=5012.2,5016.5
Exp/Cntr=0.3,0.1

Chan Stop Cuts=-1