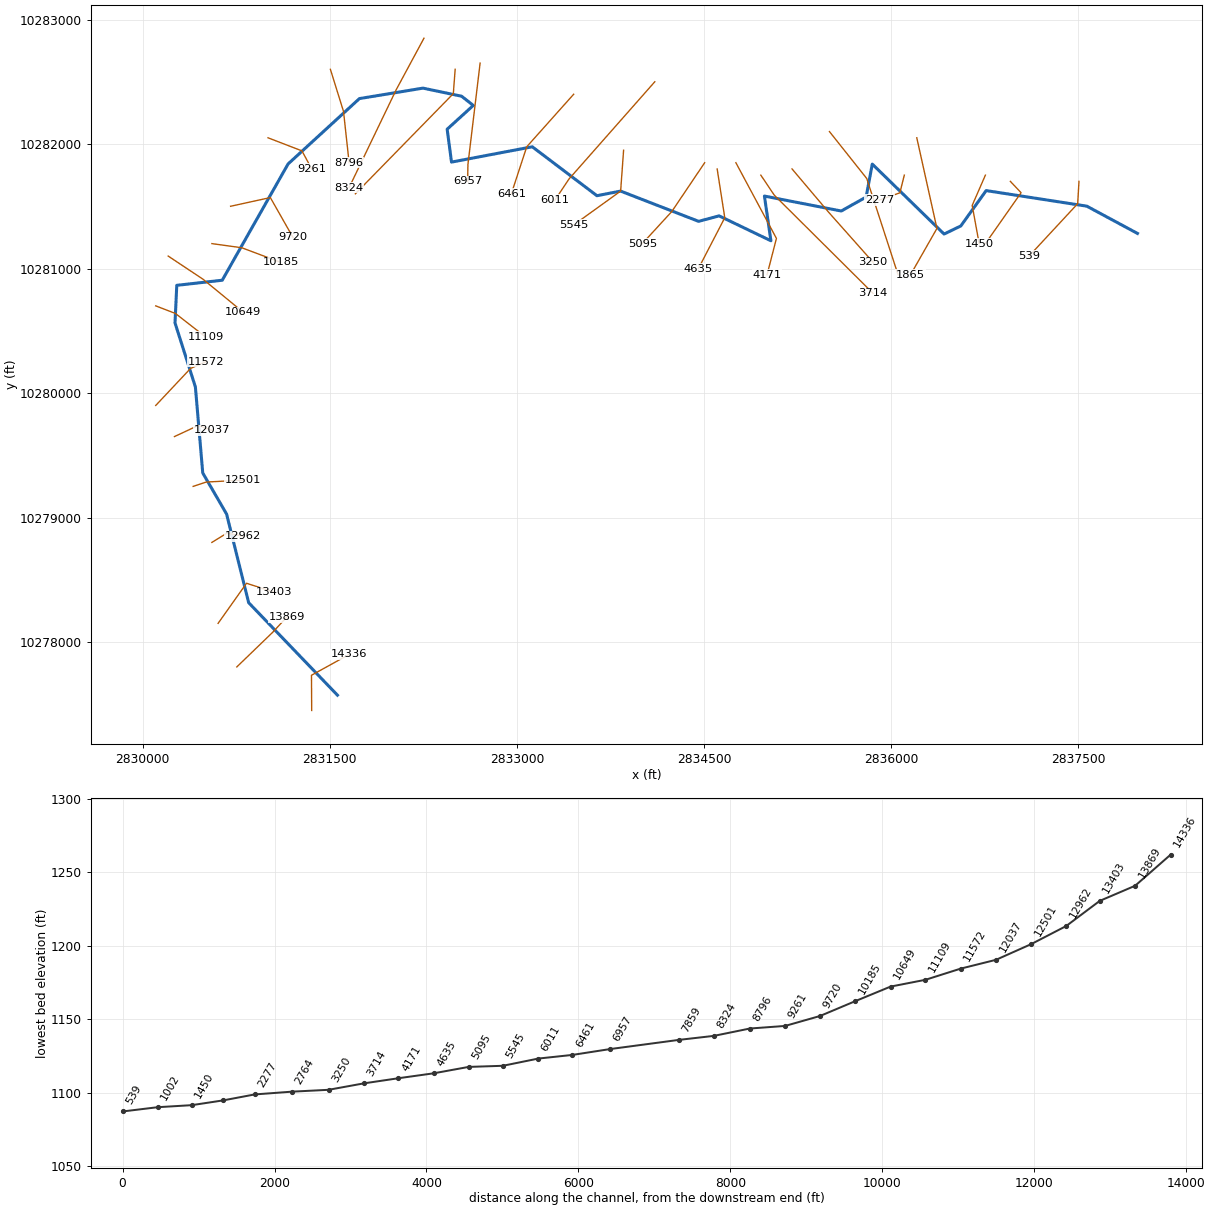
--- LITTLE LLANO 056.prj (project) ---

Proj Title=LITTLE LLANO 056 Base Level Engineering
Current Plan=p01
Default Exp/Contr=0.3,0.1
English Units
Geom File=g01
Flow File=f01
Plan File=p01
BEGIN DESCRIPTION:
LITTLE LLANO 056
END DESCRIPTION:

--- LITTLE LLANO 056.p01 (plan) ---

Plan Title=Multiple Run
Short Identifier=Multiple
Geom File=g01
Flow File=f01
Subcritical Flow
K Sum by GR= 0
Std Step Tol= 0.01
Critical Tol= 0.01
Num of Std Step Trials= 20
Max Error Tol= 0.3
Flow Tol Ratio= 0.001
Split Flow NTrial= 30
Split Flow Tol= 0.02
Split Flow Ratio= 0.02
Log Output Level= 0
Friction Slope Method= 1
Unsteady Friction Slope Method= 2
Unsteady Bridges Friction Slope Method= 1
Parabolic Critical Depth
Global Vel Dist=  1 , 1 , 1
Global Log Level= 0
CheckData=True
Encroach Param= -1, 0, 0, 0
BEGIN DESCRIPTION:
Multiple Run
END DESCRIPTION:

--- LITTLE LLANO 056.f01 (steady flow) ---

Flow Title=Multiple
Number of Profiles=7
Profile Names=10-year,25-year,50-year,1pct_min,100-year,1pct_plu,500-year
River Rch & RM= LITTLE LLANO 056,Reach-1,14336
      41      67      97      48     144     436     352
River Rch & RM= LITTLE LLANO 056,Reach-1,9261
     104     211     338     179     541    1634    1481
River Rch & RM= LITTLE LLANO 056,Reach-1,6011
     136     287     468     251     758    2290    2124
River Rch & RM= LITTLE LLANO 056,Reach-1,2277
     148     315     515     278     839    2533    2364
Boundary for River Rch & Prof#=LITTLE LLANO 056,Reach-1,1
Up Type=0
Dn Type=3
Dn Slope=0.005
Boundary for River Rch & Prof#=LITTLE LLANO 056,Reach-1,2
Up Type=0
Dn Type=3
Dn Slope=0.005
Boundary for River Rch & Prof#=LITTLE LLANO 056,Reach-1,3
Up Type=0
Dn Type=3
Dn Slope=0.005
Boundary for River Rch & Prof#=LITTLE LLANO 056,Reach-1,4
Up Type=0
Dn Type=3
Dn Slope=0.005
Boundary for River Rch & Prof#=LITTLE LLANO 056,Reach-1,5
Up Type=0
Dn Type=3
Dn Slope=0.005
Boundary for River Rch & Prof#=LITTLE LLANO 056,Reach-1,6
Up Type=0
Dn Type=3
Dn Slope=0.005
Boundary for River Rch & Prof#=LITTLE LLANO 056,Reach-1,7
Up Type=0
Dn Type=3
Dn Slope=0.005

--- LITTLE LLANO 056.g01 (geometry) ---

Geom Title=Existing Conditions

River Reach=LITTLE LLANO 056,Reach-1
Reach XY= 30
      2831562.25     10277576.00      2830850.50     10278319.00
      2830673.50     10279031.00      2830482.50     10279361.00
      2830423.50     10280052.00      2830260.25     10280566.00
      2830274.25     10280868.00      2830638.75     10280909.00
      2831166.50     10281843.00      2831738.25     10282368.00
      2832247.50     10282452.00      2832557.25     10282387.00
      2832651.00     10282313.00      2832441.50     10282122.00
      2832476.50     10281858.00      2833123.75     10281981.00
      2833642.00     10281588.00      2833832.00     10281625.00
      2834457.00     10281382.00      2834621.25     10281426.00
      2835036.50     10281226.00      2834984.50     10281585.00
      2835600.25     10281465.00      2835799.50     10281577.00
      2835849.00     10281842.00      2836424.50     10281280.00
      2836558.75     10281345.00      2836761.75     10281629.00
      2837568.50     10281504.00      2837974.50     10281285.00

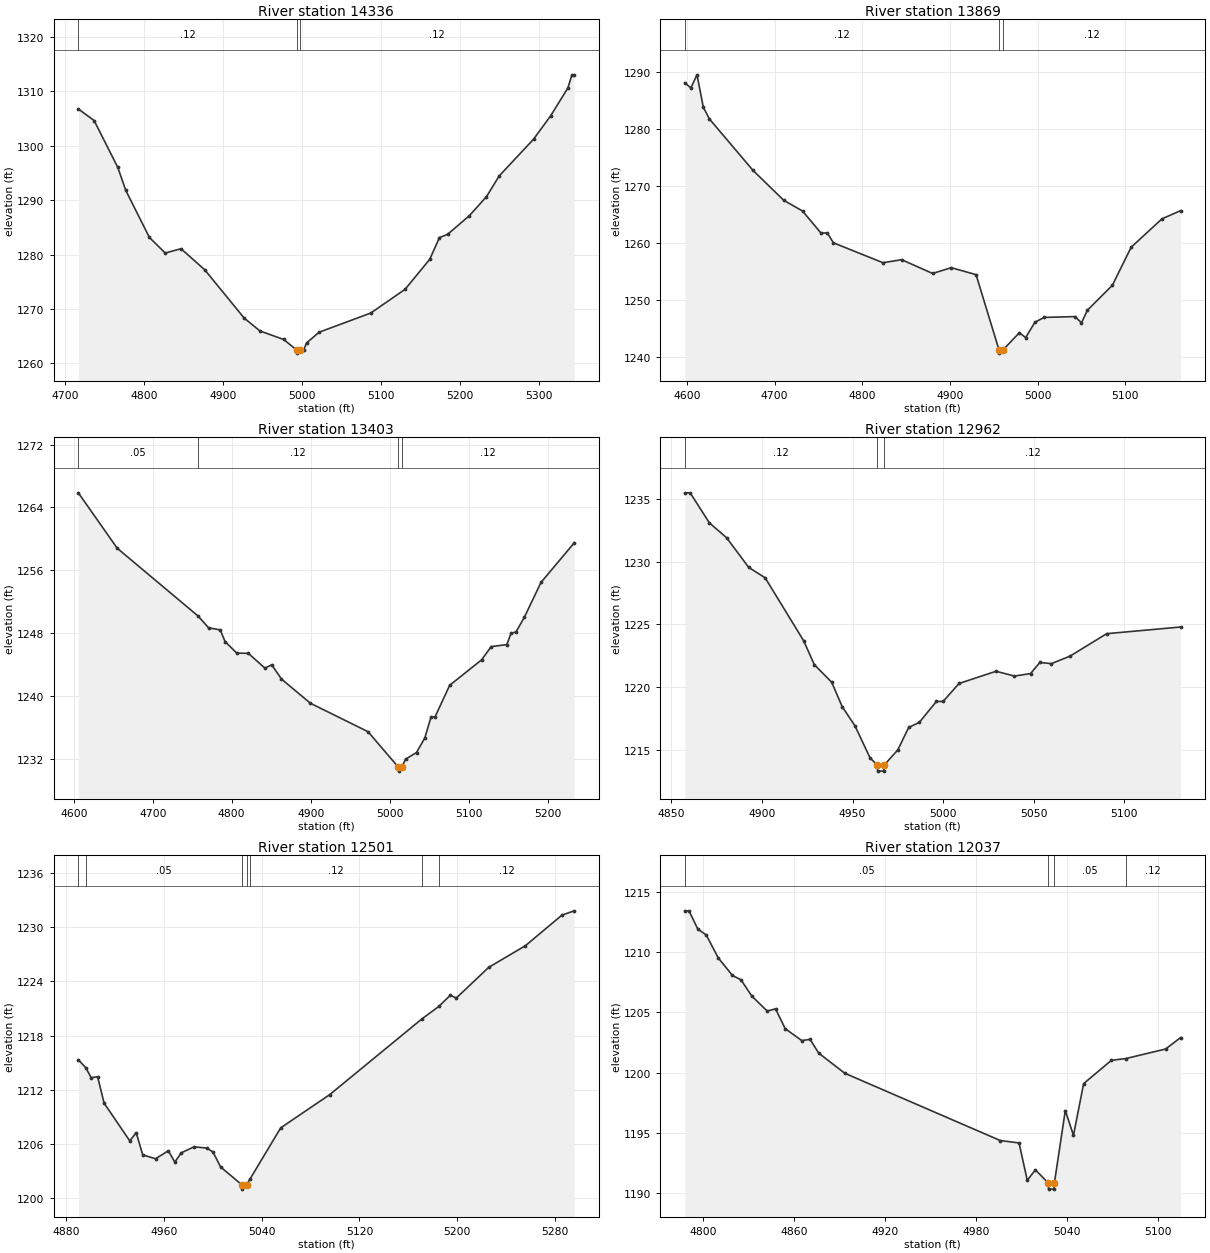
Type RM Length L Ch R = 1,14336,467,467,467
BEGIN DESCRIPTION:
LITTLE LLANO 056 30.0
END DESCRIPTION:
XS GIS Cut Line= 3
      2831355.68     10277453.11      2831354.00     10277736.00
      2831655.70     10277903.12
#Sta/Elev= 30
  4717.1 1306.77  4737.1 1304.64  4767.1 1296.01  4777.1 1291.81  4807.1 1283.14
  4827.1 1280.28  4847.1 1281.07  4877.1 1277.20  4927.1 1268.31  4947.1 1265.94
  4977.1 1264.38  4994.1 1262.37  4994.3 1261.87  4998.1 1262.37  5002.2 1262.37
  5006.0 1263.74  5022.0 1265.72  5087.3 1269.24  5130.8 1273.61  5162.0 1279.13
  5174.3 1283.12  5184.6 1283.71  5212.1 1287.14  5233.8 1290.64  5249.9 1294.45
  5293.4 1301.21  5315.1 1305.52  5336.9 1310.64  5342.0 1313.05  5344.9 1313.05
#Mann=3,-1,0
  4717.1    0.12       0  4994.1    0.07       0  4998.1    0.12       0
Bank Sta=4994.1,4998.1
Exp/Cntr=0.3,0.1

Type RM Length L Ch R = 1,13869,466,466,466
BEGIN DESCRIPTION:
LITTLE LLANO 056 29.0
END DESCRIPTION:
XS GIS Cut Line= 3
      2830755.72     10277803.14      2831045.00     10278083.00
      2831155.66     10278203.09
#Sta/Elev= 30
  4597.5 1288.09  4604.5 1287.21  4611.5 1289.49  4618.7 1283.82  4625.6 1281.77
  4675.3 1272.76  4710.5 1267.50  4731.9 1265.63  4753.0 1261.76  4760.2 1261.80
  4767.1 1260.06  4823.7 1256.57  4845.0 1257.10  4880.3 1254.69  4901.6 1255.70
  4929.9 1254.48  4956.2 1241.23  4956.5 1240.73  4960.2 1241.23  4979.3 1244.30
  4986.5 1243.45  4997.0 1246.14  5007.7 1246.99  5042.8 1247.13  5050.2 1246.04
  5057.0 1248.26  5085.4 1252.61  5106.9 1259.29  5142.1 1264.27  5163.3 1265.69
#Mann=3,-1,0
  4597.5    0.12       0  4956.2    0.07       0  4960.2    0.12       0
Bank Sta=4956.2,4960.2
Exp/Cntr=0.3,0.1

Type RM Length L Ch R = 1,13403,441,441,441
BEGIN DESCRIPTION:
LITTLE LLANO 056 28.0
END DESCRIPTION:
XS GIS Cut Line= 3
      2830605.69     10278153.12      2830833.25     10278475.00
      2831055.72     10278403.10
#Sta/Elev= 30
  4605.8 1265.86  4655.0 1258.81  4757.4 1250.18  4770.7 1248.68  4785.5 1248.41
  4791.6 1246.93  4806.4 1245.46  4821.2 1245.42  4842.1 1243.54  4850.7 1243.97
  4863.0 1242.16  4899.7 1239.07  4972.7 1235.45  5011.1 1230.93  5011.3 1230.43
  5015.1 1230.93  5020.4 1231.96  5034.1 1232.80  5044.6 1234.65  5052.4 1237.30
  5057.6 1237.35  5076.1 1241.36  5116.4 1244.59  5128.7 1246.28  5148.5 1246.54
  5153.7 1247.96  5160.2 1248.17  5170.7 1250.03  5191.7 1254.45  5233.8 1259.49
#Mann=4,-1,0
  4605.8    0.05       0  4757.4    0.12       0  5011.1    0.07       0
  5015.1    0.12       0
Bank Sta=5011.1,5015.1
Exp/Cntr=0.3,0.1

Type RM Length L Ch R = 1,12962,461,461,461
BEGIN DESCRIPTION:
LITTLE LLANO 056 27.0
END DESCRIPTION:
XS GIS Cut Line= 3
      2830555.66     10278803.10      2830677.00     10278878.00
      2830805.71     10278853.11
#Sta/Elev= 30
  4857.4 1235.47  4860.4 1235.47  4871.0 1233.08  4880.5 1231.90  4892.7 1229.54
  4901.8 1228.71  4923.1 1223.69  4928.9 1221.81  4938.5 1220.41  4944.3 1218.47
  4951.4 1216.93  4959.7 1214.39  4963.6 1213.84  4963.9 1213.34  4967.4 1213.34
  4967.6 1213.84  4975.0 1215.03  4981.0 1216.81  4986.9 1217.22  4996.3 1218.88
  5000.0 1218.88  5008.8 1220.31  5029.2 1221.28  5039.4 1220.90  5048.3 1221.10
  5053.4 1221.98  5059.8 1221.89  5070.0 1222.48  5090.3 1224.27  5131.1 1224.80
#Mann=3,-1,0
  4857.4    0.12       0  4963.6    0.07       0  4967.6    0.12       0
Bank Sta=4963.6,4967.6
Exp/Cntr=0.3,0.1

Type RM Length L Ch R = 1,12501,464,464,464
BEGIN DESCRIPTION:
LITTLE LLANO 056 26.0
END DESCRIPTION:
XS GIS Cut Line= 3
      2830405.72     10279253.12      2830510.25     10279288.00
      2830805.66     10279303.11
#Sta/Elev= 30
  4889.8 1215.33  4896.0 1214.43  4900.3 1213.35  4905.6 1213.45  4910.9 1210.53
  4931.9 1206.36  4937.2 1207.26  4942.5 1204.81  4953.0 1204.38  4963.5 1205.26
  4968.8 1204.01  4974.1 1205.04  4984.6 1205.70  4995.0 1205.56  5000.0 1205.13
  5006.3 1203.47  5023.5 1201.52  5023.7 1201.02  5027.5 1201.52  5030.2 1202.10
  5055.5 1207.80  5095.6 1211.47  5171.3 1219.87  5184.9 1221.22  5194.3 1222.46
  5199.3 1222.16  5225.7 1225.54  5255.8 1227.94  5285.8 1231.33  5295.8 1231.80
#Mann=7,-1,0
  4889.8    0.12       0  4896.0    0.05       0  5023.5    0.05       0
  5027.5    0.05       0  5030.2    0.12       0  5171.3    0.05       0
  5184.9    0.12       0
Bank Sta=5023.5,5027.5
Exp/Cntr=0.3,0.1

Type RM Length L Ch R = 1,12037,465,465,465
BEGIN DESCRIPTION:
LITTLE LLANO 056 25.0
END DESCRIPTION:
XS GIS Cut Line= 3
      2830255.65     10279653.09      2830447.75     10279743.00
      2830555.71     10279703.10
#Sta/Elev= 30
  4787.9 1213.41  4790.7 1213.41  4796.6 1211.88  4802.1 1211.41  4810.0 1209.51
  4819.4 1208.05  4825.0 1207.69  4832.1 1206.35  4842.3 1205.10  4847.8 1205.28
  4854.2 1203.64  4865.1 1202.65  4870.6 1202.75  4876.3 1201.61  4893.5 1199.94
  4996.1 1194.36  5008.5 1194.16  5013.9 1191.06  5019.3 1191.93  5027.8 1190.83
  5028.0 1190.33  5031.5 1190.33  5031.8 1190.83  5039.0 1196.85  5044.4 1194.79
  5051.1 1199.08  5069.4 1201.01  5079.0 1201.16  5105.2 1201.95  5115.1 1202.90
#Mann=4,-1,0
  4787.9    0.05       0  5027.8    0.05       0  5031.8    0.05       0
  5079.0    0.12       0
Bank Sta=5027.8,5031.8
Exp/Cntr=0.3,0.1

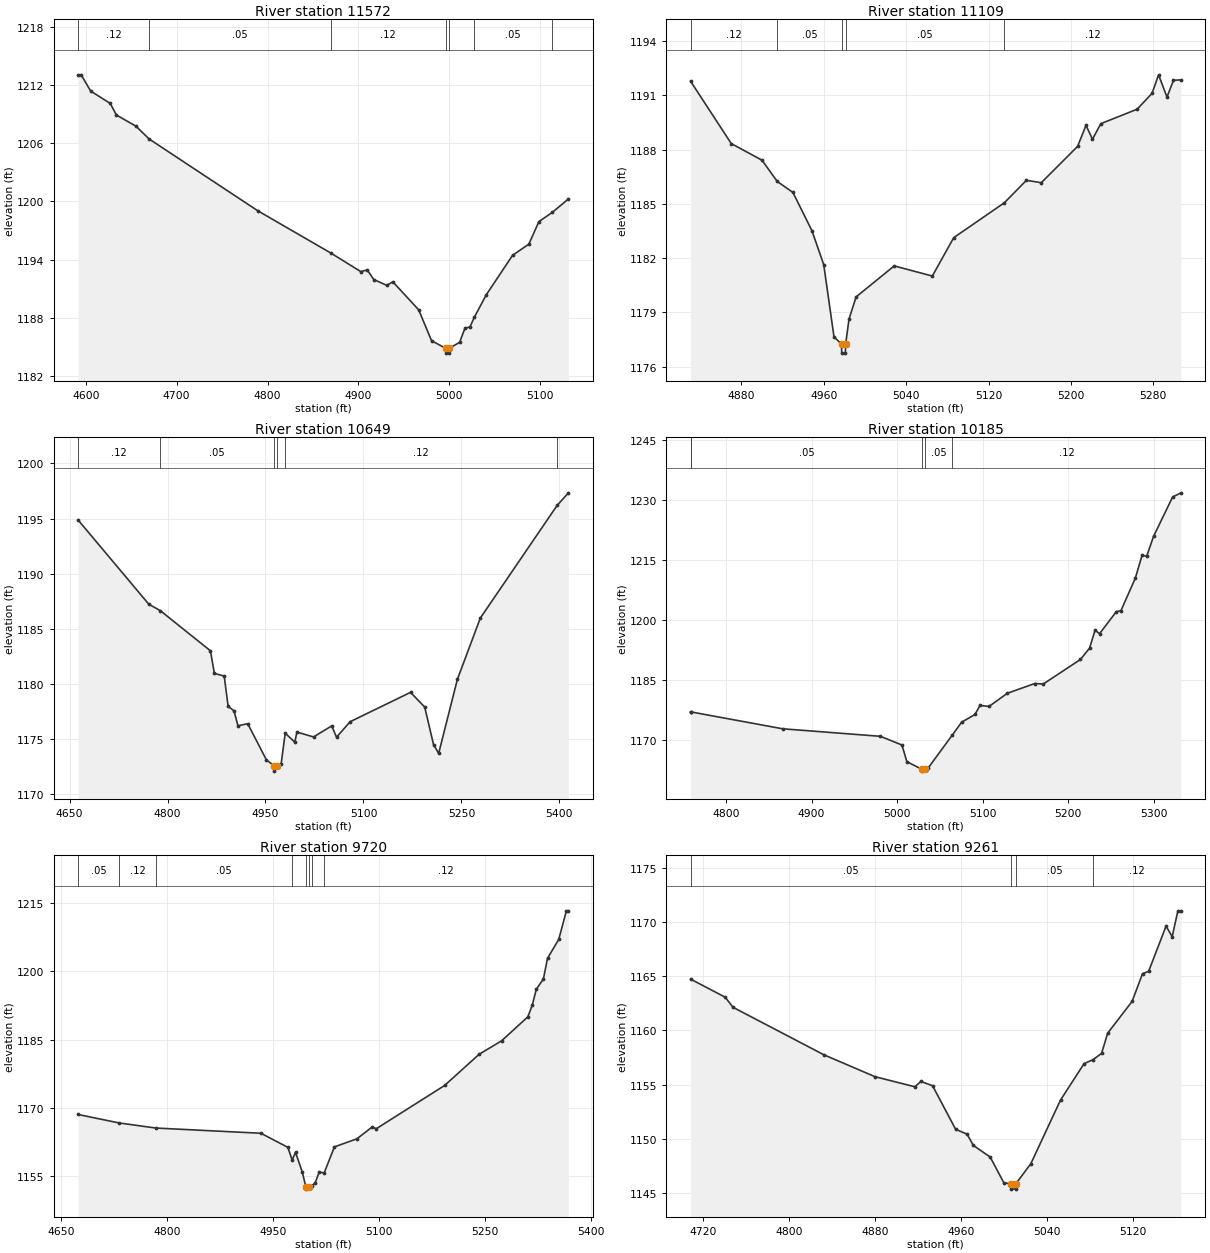
Type RM Length L Ch R = 1,11572,463,463,463
BEGIN DESCRIPTION:
LITTLE LLANO 056 24.0
END DESCRIPTION:
XS GIS Cut Line= 3
      2830105.70     10279903.13      2830385.25     10280201.00
      2830505.66     10280253.10
#Sta/Elev= 30
  4591.5 1213.08  4594.9 1213.08  4605.4 1211.40  4626.9 1210.13  4633.7 1208.93
  4655.2 1207.78  4669.8 1206.45  4789.5 1199.03  4870.0 1194.66  4902.8 1192.75
  4909.7 1192.94  4917.0 1191.94  4931.2 1191.34  4938.0 1191.70  4966.4 1188.81
  4980.5 1185.63  4996.0 1184.84  4996.3 1184.34  4999.8 1184.34  5000.0 1184.84
  5011.4 1185.45  5017.4 1186.93  5022.8 1187.04  5027.5 1188.02  5040.8 1190.37
  5069.8 1194.45  5087.6 1195.59  5098.7 1197.92  5113.5 1198.88  5131.2 1200.26
#Mann=7,-1,0
  4591.5    0.12       0  4669.8    0.05       0  4870.0    0.12       0
  4996.0    0.07       0  5000.0    0.12       0  5027.5    0.05       0
  5113.5    0.12       0
Bank Sta=4996,5000
Exp/Cntr=0.3,0.1

Type RM Length L Ch R = 1,11109,460,460,460
BEGIN DESCRIPTION:
LITTLE LLANO 056 23.0
END DESCRIPTION:
XS GIS Cut Line= 3
      2830105.65     10280703.12      2830263.75     10280642.00
      2830505.65     10280453.14
#Sta/Elev= 30
  4830.5 1191.78  4870.1 1188.33  4900.0 1187.41  4914.7 1186.24  4930.0 1185.63
  4948.5 1183.51  4959.9 1181.64  4969.9 1177.65  4977.2 1177.25  4977.4 1176.75
  4980.9 1176.75  4981.2 1177.25  4984.5 1178.64  4991.4 1179.86  5028.4 1181.57
  5065.4 1181.01  5086.2 1183.13  5135.4 1185.06  5156.8 1186.30  5171.3 1186.17
  5206.6 1188.18  5214.7 1189.34  5221.0 1188.57  5229.1 1189.43  5264.4 1190.23
  5278.9 1191.11  5285.2 1192.13  5293.4 1190.90  5299.7 1191.83  5306.9 1191.85
#Mann=5,-1,0
  4830.5    0.12       0  4914.7    0.05       0  4977.2    0.05       0
  4981.2    0.05       0  5135.4    0.12       0
Bank Sta=4977.2,4981.2
Exp/Cntr=0.3,0.1

Type RM Length L Ch R = 1,10649,464,464,464
BEGIN DESCRIPTION:
LITTLE LLANO 056 22.0
END DESCRIPTION:
XS GIS Cut Line= 3
      2830205.71     10281103.10      2830486.00     10280916.00
      2830805.69     10280653.11
#Sta/Elev= 30
  4663.0 1194.88  4771.2 1187.25  4789.1 1186.65  4865.7 1183.02  4871.7 1180.97
  4886.8 1180.73  4892.8 1177.98  4901.8 1177.58  4907.8 1176.22  4922.8 1176.41
  4951.5 1173.12  4962.9 1172.61  4963.1 1172.11  4966.9 1172.61  4973.9 1172.73
  4980.2 1175.55  4994.9 1174.73  4998.1 1175.65  5023.6 1175.21  5051.4 1176.21
  5058.8 1175.19  5079.6 1176.59  5172.1 1179.25  5193.8 1177.92  5207.3 1174.52
  5215.2 1173.72  5243.8 1180.42  5279.0 1185.99  5396.6 1196.20  5413.9 1197.34
#Mann=6,-1,0
  4663.0    0.12       0  4789.1    0.05       0  4962.9    0.07       0
  4966.9    0.05       0  4980.2    0.12       0  5396.6    0.05       0
Bank Sta=4962.9,4966.9
Exp/Cntr=0.3,0.1

Type RM Length L Ch R = 1,10185,465,465,465
BEGIN DESCRIPTION:
LITTLE LLANO 056 21.0
END DESCRIPTION:
XS GIS Cut Line= 3
      2830555.68     10281203.11      2830795.00     10281170.00
      2831105.64     10281053.13
#Sta/Elev= 30
  4758.4 1176.99  4759.2 1176.99  4866.1 1172.79  4980.5 1170.91  5005.7 1168.74
  5011.4 1164.59  5028.6 1162.72  5028.9 1162.22  5032.6 1162.72  5035.9 1162.88
  5064.3 1171.15  5075.5 1174.44  5091.1 1176.36  5096.9 1178.61  5107.6 1178.38
  5128.9 1181.65  5161.0 1184.09  5171.0 1183.97  5214.4 1190.09  5225.1 1192.93
  5231.5 1197.39  5236.8 1196.54  5256.4 1202.03  5261.7 1202.24  5278.5 1210.33
  5286.6 1216.13  5291.9 1215.84  5299.9 1220.81  5322.2 1230.65  5331.9 1231.69
#Mann=5,-1,0
  4758.4    0.12       0  4759.2    0.05       0  5028.6    0.05       0
  5032.6    0.05       0  5064.3    0.12       0
Bank Sta=5028.6,5032.6
Exp/Cntr=0.3,0.1

Type RM Length L Ch R = 1,9720,459,459,459
BEGIN DESCRIPTION:
LITTLE LLANO 056 20.0
END DESCRIPTION:
XS GIS Cut Line= 3
      2830705.73     10281503.12      2831024.25     10281573.00
      2831205.70     10281253.08
#Sta/Elev= 30
  4673.9 1168.52  4732.0 1166.66  4784.0 1165.54  4932.7 1164.39  4970.8 1161.29
  4976.8 1158.51  4981.6 1160.18  4991.2 1155.87  4996.2 1152.60  4996.4 1152.10
  5000.2 1152.60  5004.5 1152.82  5009.3 1153.44  5015.1 1155.83  5022.2 1155.69
  5036.7 1161.40  5068.5 1163.17  5090.1 1165.78  5095.9 1165.39  5192.5 1174.90
  5241.5 1181.78  5273.3 1184.74  5310.3 1190.00  5316.6 1192.54  5322.3 1196.07
  5332.4 1198.34  5338.2 1202.89  5354.1 1207.05  5364.9 1213.33  5367.8 1213.33
#Mann=8,-1,0
  4673.9    0.05       0  4732.0    0.12       0  4784.0    0.05       0
  4976.8    0.12       0  4996.2    0.07       0  5000.2    0.12       0
  5004.5    0.05       0  5022.2    0.12       0
Bank Sta=4996.2,5000.2
Exp/Cntr=0.3,0.1

Type RM Length L Ch R = 1,9261,465,465,465
BEGIN DESCRIPTION:
LITTLE LLANO 056 19.0
END DESCRIPTION:
XS GIS Cut Line= 3
      2831005.65     10282053.12      2831277.75     10281948.00
      2831355.68     10281803.13
#Sta/Elev= 30
  4708.3 1164.74  4740.5 1163.07  4747.9 1162.13  4832.4 1157.75  4879.9 1155.73
  4916.9 1154.80  4922.7 1155.29  4933.5 1154.89  4954.9 1150.88  4965.6 1150.42
  4971.5 1149.38  4987.1 1148.31  4999.8 1145.93  5006.5 1145.85  5006.8 1145.35
  5010.7 1145.35  5011.0 1145.85  5024.9 1147.70  5052.5 1153.57  5074.4 1156.93
  5082.9 1157.31  5090.7 1157.88  5096.4 1159.75  5119.1 1162.68  5128.8 1165.24
  5134.5 1165.46  5150.7 1169.63  5156.4 1168.66  5161.7 1171.04  5164.5 1171.04
#Mann=4,-1,0
  4708.3    0.05       0  5006.5    0.03       0  5011.0    0.05       0
  5082.9    0.12       0
Bank Sta=5006.5,5011
Exp/Cntr=0.3,0.1

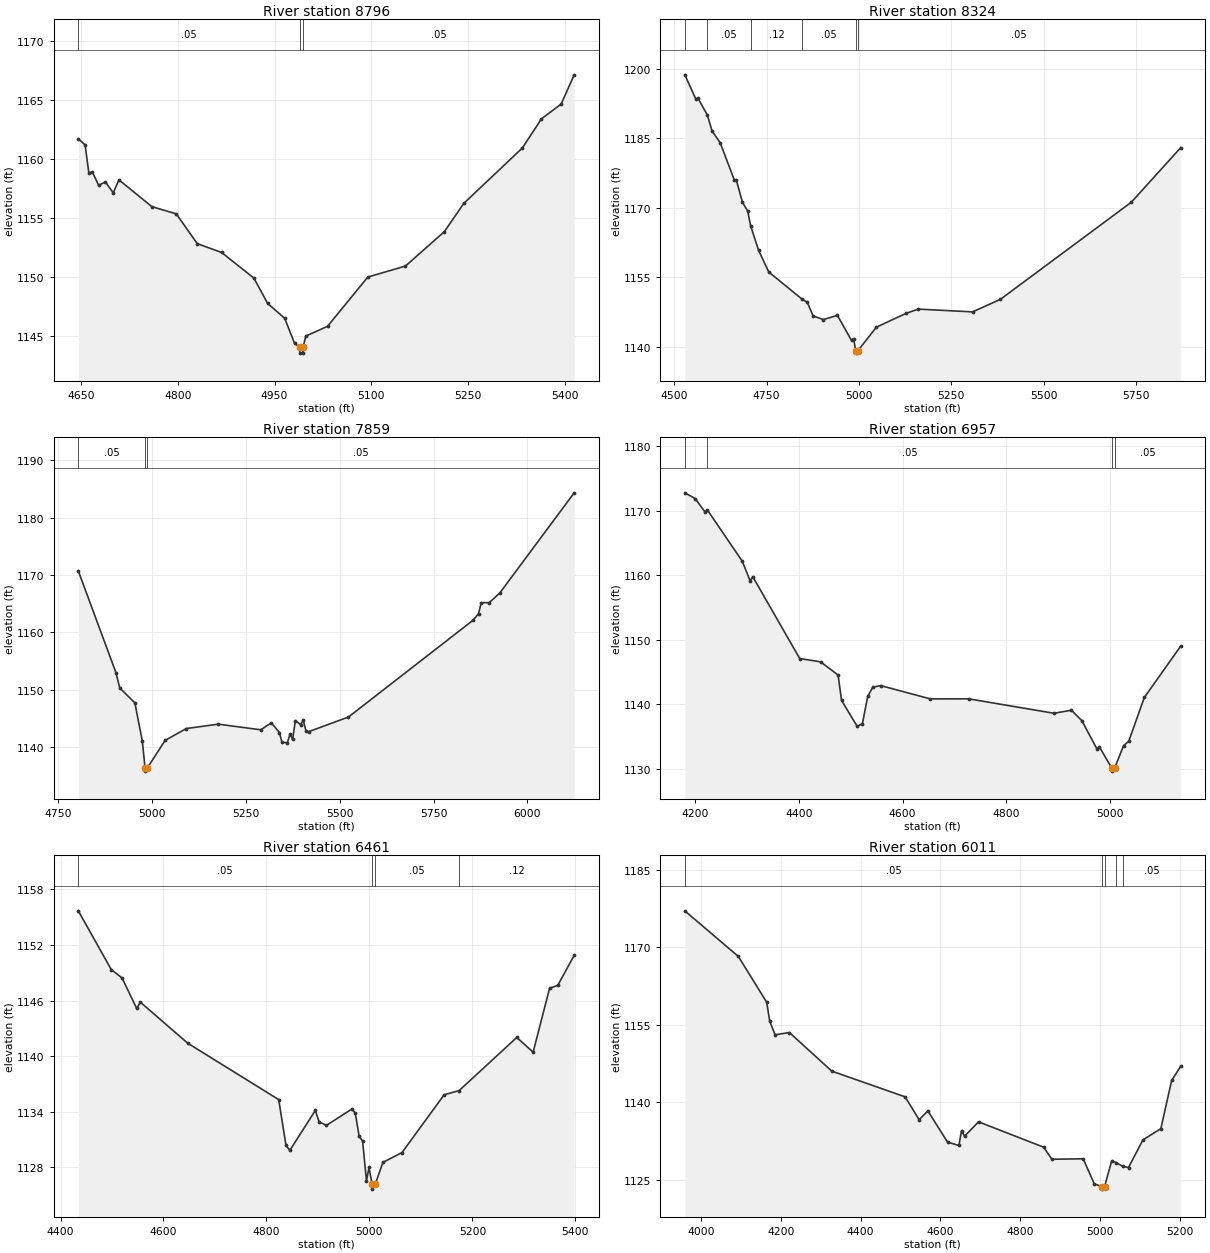
Type RM Length L Ch R = 1,8796,472,472,472
BEGIN DESCRIPTION:
LITTLE LLANO 056 18.0
END DESCRIPTION:
XS GIS Cut Line= 3
      2831505.67     10282603.15      2831610.75     10282265.00
      2831655.68     10281853.14
#Sta/Elev= 30
  4645.9 1161.72  4656.4 1161.21  4662.2 1158.83  4667.5 1158.93  4677.4 1157.79
  4687.8 1158.07  4700.0 1157.15  4708.8 1158.25  4759.9 1155.98  4797.7 1155.37
  4830.2 1152.85  4868.0 1152.10  4918.2 1149.92  4939.1 1147.80  4965.7 1146.53
  4981.0 1144.41  4988.8 1144.08  4989.2 1143.58  4993.8 1143.58  4994.3 1144.08
  4998.3 1145.02  5032.1 1145.85  5094.5 1150.02  5152.8 1150.95  5213.1 1153.86
  5243.3 1156.26  5333.9 1160.94  5363.6 1163.41  5394.2 1164.67  5414.3 1167.14
#Mann=3,-1,0
  4645.9    0.05       0  4988.8    0.03       0  4994.3    0.05       0
Bank Sta=4988.8,4994.3
Exp/Cntr=0.3,0.1

Type RM Length L Ch R = 1,8324,465,465,465
BEGIN DESCRIPTION:
LITTLE LLANO 056 17.0
END DESCRIPTION:
XS GIS Cut Line= 3
      2832255.68     10282853.11      2832032.50     10282438.00
      2831655.66     10281653.07
#Sta/Elev= 30
  4528.7 1198.70  4558.7 1193.45  4564.4 1193.64  4589.8 1190.02  4602.5 1186.56
  4624.5 1184.03  4662.6 1176.00  4668.3 1175.92  4684.5 1171.23  4699.0 1169.24
  4707.0 1166.07  4728.3 1160.81  4755.9 1156.12  4846.2 1150.24  4859.8 1149.62
  4876.1 1146.63  4903.6 1145.84  4941.8 1146.75  4979.9 1141.32  4985.6 1141.73
  4991.4 1139.09  4991.8 1138.59  4997.0 1139.09  5047.3 1144.20  5127.4 1147.17
  5160.6 1148.10  5307.5 1147.50  5382.6 1150.19  5737.5 1171.20  5870.7 1182.95
#Mann=6,-1,0
  4528.7    0.12       0  4589.8    0.05       0  4707.0    0.12       0
  4846.2    0.05       0  4991.4    0.05       0  4997.0    0.05       0
Bank Sta=4991.4,4997
Exp/Cntr=0.3,0.1

Type RM Length L Ch R = 1,7859,902,902,902
BEGIN DESCRIPTION:
LITTLE LLANO 056 16.0
END DESCRIPTION:
XS GIS Cut Line= 3
      2832505.69     10282603.15      2832491.00     10282408.00
      2831705.70     10281603.13
#Sta/Elev= 30
  4804.3 1170.69  4904.6 1152.95  4914.6 1150.31  4954.8 1147.73  4974.8 1141.01
  4982.0 1136.33  4982.5 1135.83  4987.6 1136.33  5035.4 1141.19  5092.0 1143.25
  5176.9 1144.01  5290.0 1143.03  5318.3 1144.25  5339.6 1142.55  5346.6 1140.84
  5360.8 1140.78  5367.9 1142.26  5374.9 1141.36  5382.1 1144.62  5396.2 1143.94
  5403.2 1144.68  5410.4 1142.87  5417.3 1142.70  5523.5 1145.25  5855.9 1162.14
  5870.0 1163.27  5877.0 1165.16  5898.3 1165.17  5926.6 1166.86  6124.5 1184.30
#Mann=3,-1,0
  4804.3    0.05       0  4982.0    0.03       0  4987.6    0.05       0
Bank Sta=4982,4987.6
Exp/Cntr=0.3,0.1

Type RM Length L Ch R = 1,6957,496,496,496
BEGIN DESCRIPTION:
LITTLE LLANO 056 15.0
END DESCRIPTION:
XS GIS Cut Line= 3
      2832705.69     10282653.16      2832608.00     10281839.00
      2832605.68     10281703.12
#Sta/Elev= 30
  4180.0 1172.80  4200.2 1171.90  4218.7 1169.86  4223.7 1170.12  4290.8 1162.19
  4306.0 1159.12  4311.0 1159.79  4401.6 1147.08  4441.9 1146.57  4475.5 1144.52
  4482.2 1140.59  4512.4 1136.55  4522.5 1136.98  4532.6 1141.21  4542.6 1142.65
  4557.8 1142.88  4653.4 1140.82  4727.3 1140.83  4891.8 1138.59  4925.4 1139.06
  4945.5 1137.44  4974.1 1133.12  4979.1 1133.40  5003.0 1130.11  5003.5 1129.61
  5008.8 1130.11  5025.9 1133.57  5035.9 1134.25  5065.9 1141.04  5135.9 1148.99
#Mann=4,-1,0
  4180.0    0.12       0  4223.7    0.05       0  5003.0    0.05       0
  5008.8    0.05       0
Bank Sta=5003,5008.8
Exp/Cntr=0.3,0.1

Type RM Length L Ch R = 1,6461,450,450,450
BEGIN DESCRIPTION:
LITTLE LLANO 056 14.0
END DESCRIPTION:
XS GIS Cut Line= 3
      2833455.68     10282403.10      2833079.50     10281981.00
      2832955.67     10281603.07
#Sta/Elev= 30
  4434.6 1155.69  4498.5 1149.35  4519.5 1148.44  4547.9 1145.15  4555.1 1145.82
  4647.4 1141.38  4823.8 1135.30  4838.0 1130.36  4845.5 1129.82  4894.9 1134.13
  4902.4 1132.89  4916.6 1132.52  4965.9 1134.28  4972.6 1133.83  4980.1 1131.33
  4986.8 1130.82  4994.3 1126.50  4999.1 1127.97  5005.4 1126.13  5005.9 1125.63
  5011.2 1126.13  5026.2 1128.52  5063.3 1129.58  5145.1 1135.82  5174.2 1136.27
  5286.2 1142.01  5318.0 1140.43  5349.9 1147.31  5366.1 1147.66  5397.7 1150.88
#Mann=4,-1,0
  4434.6    0.05       0  5005.4    0.05       0  5011.2    0.05       0
  5174.2    0.12       0
Bank Sta=5005.4,5011.2
Exp/Cntr=0.3,0.1

Type RM Length L Ch R = 1,6011,466,466,466
BEGIN DESCRIPTION:
LITTLE LLANO 056 13.0
END DESCRIPTION:
XS GIS Cut Line= 3
      2834105.69     10282503.12      2833418.00     10281722.00
      2833305.70     10281553.13
#Sta/Elev= 30
  3959.3 1177.07  4093.6 1168.23  4164.7 1159.36  4172.3 1155.67  4185.8 1153.04
  4221.6 1153.49  4327.9 1146.01  4511.9 1141.02  4547.1 1136.58  4568.9 1138.31
  4618.2 1132.25  4646.7 1131.60  4653.3 1134.46  4660.9 1133.40  4696.0 1136.18
  4859.2 1131.27  4880.1 1128.93  4958.5 1129.02  4986.3 1124.15  5005.8 1123.64
  5006.3 1123.14  5012.1 1123.64  5030.0 1128.63  5041.1 1128.29  5057.3 1127.56
  5072.1 1127.33  5108.1 1132.67  5153.2 1134.86  5180.3 1144.20  5202.8 1146.93
#Mann=5,-1,0
  3959.3    0.05       0  5005.8    0.05       0  5012.1    0.05       0
  5041.1    0.12       0  5057.3    0.05       0
Bank Sta=5005.8,5012.1
Exp/Cntr=0.3,0.1

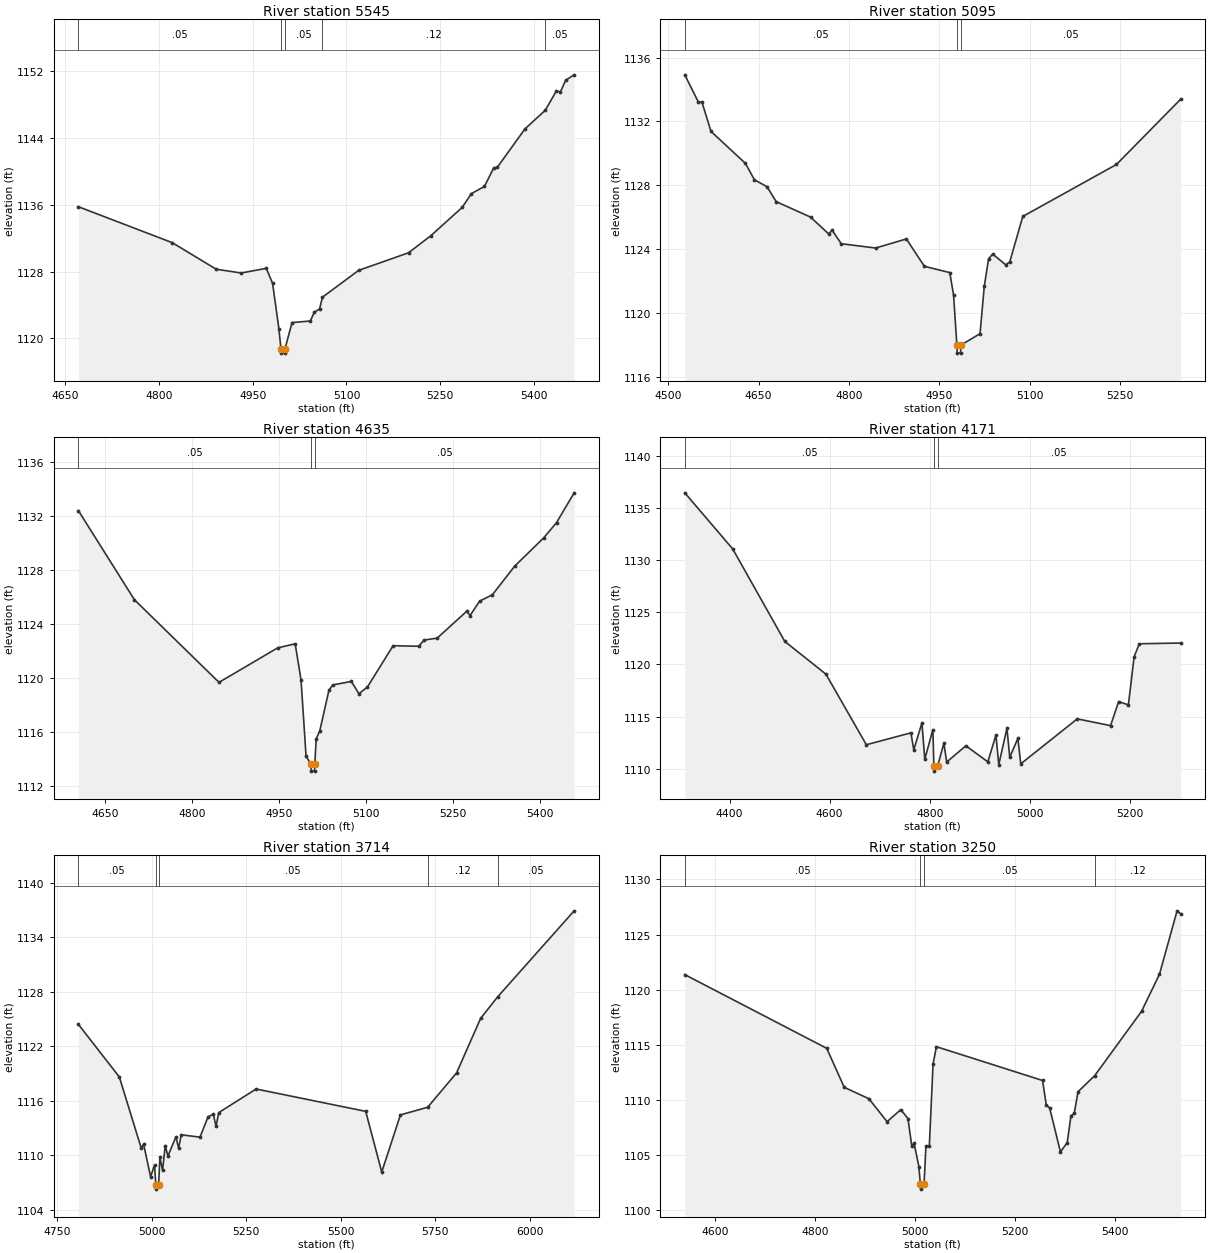
Type RM Length L Ch R = 1,5545,450,450,450
BEGIN DESCRIPTION:
LITTLE LLANO 056 12.0
END DESCRIPTION:
XS GIS Cut Line= 3
      2833855.69     10281953.15      2833832.00     10281625.00
      2833455.65     10281353.09
#Sta/Elev= 30
  4671.0 1135.77  4821.4 1131.46  4891.6 1128.28  4931.7 1127.83  4971.8 1128.39
  4981.8 1126.58  4991.9 1121.15  4995.2 1118.73  4995.7 1118.23  5001.1 1118.23
  5001.6 1118.73  5012.9 1121.89  5042.3 1122.08  5048.4 1123.12  5057.0 1123.53
  5061.6 1124.93  5119.6 1128.15  5199.3 1130.25  5234.9 1132.29  5285.2 1135.69
  5299.9 1137.34  5320.8 1138.20  5335.5 1140.41  5341.6 1140.52  5385.7 1145.10
  5418.2 1147.33  5436.0 1149.66  5442.2 1149.51  5450.7 1150.92  5464.3 1151.57
#Mann=5,-1,0
  4671.0    0.05       0  4995.2    0.03       0  5001.6    0.05       0
  5061.6    0.12       0  5418.2    0.05       0
Bank Sta=4995.2,5001.6
Exp/Cntr=0.3,0.1

Type RM Length L Ch R = 1,5095,460,460,460
BEGIN DESCRIPTION:
LITTLE LLANO 056 11.0
END DESCRIPTION:
XS GIS Cut Line= 3
      2834505.69     10281853.12      2834242.25     10281461.00
      2834005.66     10281203.08
#Sta/Elev= 30
  4527.6 1134.92  4550.1 1133.21  4556.1 1133.20  4571.1 1131.37  4628.1 1129.37
  4643.1 1128.34  4664.1 1127.90  4679.1 1126.97  4736.1 1126.00  4766.1 1124.95
  4772.1 1125.17  4787.1 1124.33  4844.1 1124.06  4895.1 1124.63  4925.1 1122.91
  4967.1 1122.52  4973.4 1121.11  4978.9 1117.97  4979.4 1117.47  4984.9 1117.47
  4985.4 1117.97  5017.3 1118.69  5024.3 1121.65  5031.5 1123.39  5038.3 1123.68
  5059.8 1123.01  5066.6 1123.19  5088.2 1126.04  5243.6 1129.30  5350.0 1133.39
#Mann=3,-1,0
  4527.6    0.05       0  4978.9    0.03       0  4985.4    0.05       0
Bank Sta=4978.9,4985.4
Exp/Cntr=0.3,0.1

Type RM Length L Ch R = 1,4635,464,464,464
BEGIN DESCRIPTION:
LITTLE LLANO 056 10.0
END DESCRIPTION:
XS GIS Cut Line= 3
      2834605.69     10281803.07      2834666.75     10281411.00
      2834455.67     10281003.08
#Sta/Elev= 30
  4603.2 1132.38  4700.0 1125.79  4846.1 1119.68  4947.3 1122.23  4977.6 1122.53
  4987.7 1119.87  4996.4 1114.23  5004.9 1113.62  5005.4 1113.12  5011.0 1113.12
  5011.5 1113.62  5013.9 1115.51  5020.1 1116.10  5036.0 1119.12  5042.7 1119.49
  5074.6 1119.75  5087.7 1118.84  5102.4 1119.34  5146.7 1122.39  5191.0 1122.35
  5200.3 1122.81  5222.8 1122.95  5273.9 1124.94  5279.5 1124.62  5296.0 1125.68
  5318.2 1126.16  5356.8 1128.28  5406.7 1130.36  5428.9 1131.49  5459.3 1133.69
#Mann=3,-1,0
  4603.2    0.05       0  5004.9    0.03       0  5011.5    0.05       0
Bank Sta=5004.9,5011.5
Exp/Cntr=0.3,0.1

Type RM Length L Ch R = 1,4171,457,457,457
BEGIN DESCRIPTION:
LITTLE LLANO 056 9.0
END DESCRIPTION:
XS GIS Cut Line= 3
      2834755.70     10281853.07      2835080.75     10281245.00
      2835005.68     10280953.10
#Sta/Elev= 30
  4310.5 1136.45  4406.4 1131.06  4510.4 1122.20  4592.5 1119.07  4673.3 1112.30
  4762.4 1113.44  4768.1 1111.81  4784.4 1114.39  4790.1 1110.91  4806.3 1113.75
  4808.3 1110.27  4808.8 1109.77  4815.7 1110.27  4828.3 1112.44  4833.9 1110.64
  4872.2 1112.20  4916.1 1110.66  4932.3 1113.22  4938.0 1110.40  4954.3 1113.88
  4959.9 1111.10  4976.2 1112.91  4981.9 1110.47  5094.9 1114.78  5161.4 1114.13
  5177.5 1116.44  5197.0 1116.12  5208.5 1120.73  5218.8 1121.98  5301.4 1122.05
#Mann=3,-1,0
  4310.5    0.05       0  4808.3    0.03       0  4815.7    0.05       0
Bank Sta=4808.3,4815.7
Exp/Cntr=0.3,0.1

Type RM Length L Ch R = 1,3714,464,464,464
BEGIN DESCRIPTION:
LITTLE LLANO 056 8.0
END DESCRIPTION:
XS GIS Cut Line= 3
      2834955.68     10281753.11      2835063.75     10281592.00
      2835855.68     10280803.12
#Sta/Elev= 30
  4806.0 1124.40  4914.4 1118.61  4972.6 1110.75  4978.6 1111.22  4997.2 1107.62
  5007.6 1108.92  5011.0 1106.76  5011.5 1106.26  5018.5 1106.76  5021.8 1109.75
  5028.9 1108.33  5035.9 1111.05  5043.0 1109.91  5064.2 1112.01  5071.3 1110.78
  5078.4 1112.24  5127.9 1111.98  5149.1 1114.21  5163.2 1114.50  5170.3 1113.16
  5177.4 1114.68  5276.4 1117.28  5566.3 1114.82  5608.7 1108.14  5658.2 1114.43
  5730.2 1115.27  5806.7 1119.05  5870.3 1125.05  5915.3 1127.42  6117.8 1136.89
#Mann=5,-1,0
  4806.0    0.05       0  5011.0    0.03       0  5018.5    0.05       0
  5730.2    0.12       0  5915.3    0.05       0
Bank Sta=5011,5018.5
Exp/Cntr=0.3,0.1

Type RM Length L Ch R = 1,3250,486,486,486
BEGIN DESCRIPTION:
LITTLE LLANO 056 7.0
END DESCRIPTION:
XS GIS Cut Line= 3
      2835205.67     10281803.12      2835502.75     10281451.00
      2835855.71     10281053.08
#Sta/Elev= 30
  4539.3 1121.36  4823.4 1114.67  4858.5 1111.13  4908.0 1110.09  4944.3 1108.01
  4971.7 1109.11  4986.0 1108.30  4993.7 1105.80  4998.4 1106.04  5007.9 1103.94
  5010.8 1102.39  5011.3 1101.89  5018.3 1102.39  5022.1 1105.82  5028.8 1105.79
  5036.3 1113.24  5043.0 1114.82  5255.5 1111.75  5263.0 1109.51  5269.7 1109.26
  5291.3 1105.27  5304.8 1106.10  5312.3 1108.52  5319.0 1108.78  5326.5 1110.73
  5359.9 1112.19  5453.7 1118.03  5489.6 1121.40  5524.8 1127.15  5531.9 1126.89
#Mann=4,-1,0
  4539.3    0.05       0  5010.8    0.03       0  5018.3    0.05       0
  5359.9    0.12       0
Bank Sta=5010.8,5018.3
Exp/Cntr=0.3,0.1

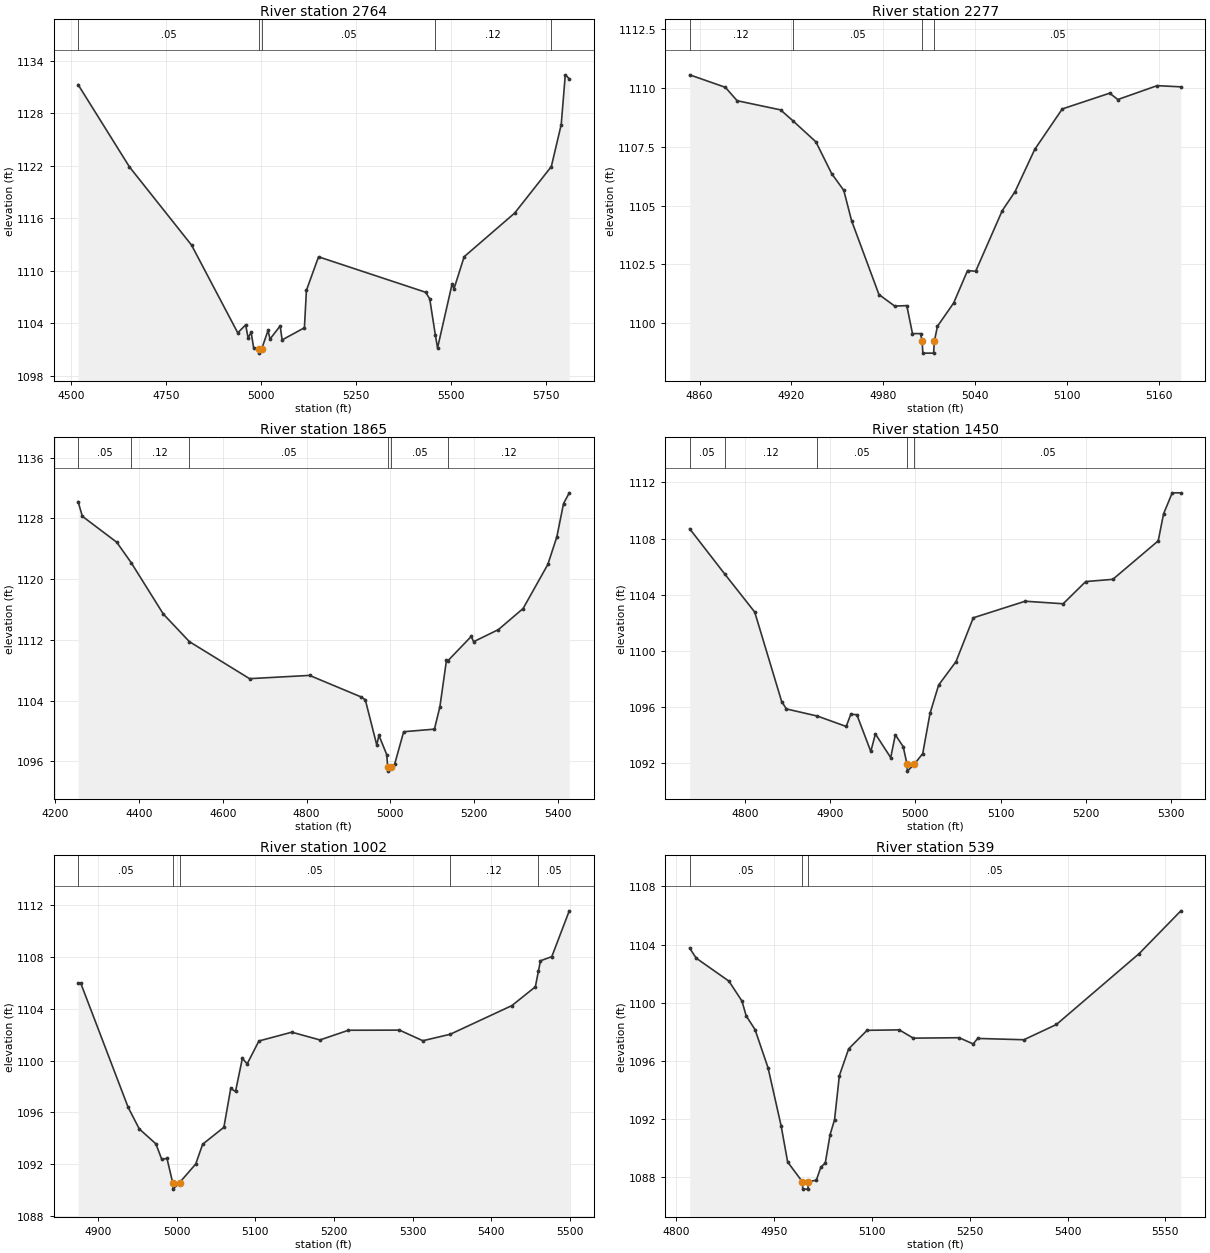
Type RM Length L Ch R = 1,2764,487,487,487
BEGIN DESCRIPTION:
LITTLE LLANO 056 6.0
END DESCRIPTION:
XS GIS Cut Line= 3
      2835505.69     10282103.11      2835804.75     10281726.00
      2836055.68     10280953.11
#Sta/Elev= 30
  4518.7 1131.30  4654.1 1121.89  4817.5 1112.96  4939.3 1102.93  4960.1 1103.84
  4966.5 1102.36  4974.6 1102.98  4981.0 1101.25  4994.8 1101.11  4995.3 1100.61
  5002.5 1101.11  5019.0 1103.20  5024.3 1102.22  5051.0 1103.72  5056.2 1102.12
  5114.9 1103.51  5120.2 1107.79  5152.1 1111.62  5434.1 1107.57  5445.0 1106.82
  5459.7 1102.71  5465.6 1101.20  5503.7 1108.47  5509.0 1107.97  5535.7 1111.63
  5668.8 1116.62  5765.3 1121.93  5791.4 1126.73  5802.1 1132.42  5812.6 1131.97
#Mann=5,-1,0
  4518.7    0.05       0  4994.8    0.03       0  5002.5    0.05       0
  5459.7    0.12       0  5765.3    0.05       0
Bank Sta=4994.8,5002.5
Exp/Cntr=0.3,0.1

Type RM Length L Ch R = 1,2277,412,412,412
BEGIN DESCRIPTION:
LITTLE LLANO 056 5.0
END DESCRIPTION:
XS GIS Cut Line= 3
      2836105.69     10281753.15      2836070.25     10281611.00
      2835905.64     10281553.10
#Sta/Elev= 30
  4853.5 1110.56  4876.8 1110.03  4884.5 1109.46  4912.9 1109.07  4920.9 1108.61
  4936.0 1107.71  4946.3 1106.36  4954.2 1105.65  4959.3 1104.36  4977.2 1101.22
  4987.5 1100.73  4995.4 1100.75  4999.1 1099.56  5004.4 1099.56  5005.4 1099.23
  5005.9 1098.73  5012.9 1098.73  5013.4 1099.23  5015.4 1099.87  5026.0 1100.86
  5035.1 1102.24  5040.4 1102.21  5057.8 1104.79  5066.1 1105.59  5079.0 1107.39
  5097.0 1109.11  5128.0 1109.78  5133.3 1109.51  5159.0 1110.10  5174.5 1110.05
#Mann=4,-1,0
  4853.5    0.12       0  4920.9    0.05       0  5005.4    0.03       0
  5013.4    0.05       0
Bank Sta=5005.4,5013.4
Exp/Cntr=0.3,0.1

Type RM Length L Ch R = 1,1865,415,415,415
BEGIN DESCRIPTION:
LITTLE LLANO 056 4.0
END DESCRIPTION:
XS GIS Cut Line= 3
      2836205.69     10282053.09      2836367.25     10281325.00
      2836155.66     10280953.07
#Sta/Elev= 30
  4254.2 1130.21  4264.4 1128.28  4346.4 1124.87  4381.3 1122.15  4457.9 1115.40
  4520.1 1111.77  4663.9 1106.89  4807.3 1107.32  4930.2 1104.49  4940.5 1104.11
  4967.9 1098.15  4973.0 1099.43  4991.7 1096.89  4994.1 1095.21  4994.6 1094.71
  5002.7 1095.21  5010.6 1095.62  5032.2 1099.90  5105.7 1100.24  5118.7 1103.17
  5134.5 1109.33  5137.3 1109.22  5193.6 1112.45  5199.4 1111.76  5258.5 1113.35
  5317.6 1116.13  5376.7 1121.94  5398.3 1125.59  5414.2 1129.96  5427.9 1131.37
#Mann=6,-1,0
  4254.2    0.05       0  4381.3    0.12       0  4520.1    0.05       0
  4994.1    0.03       0  5002.7    0.05       0  5137.3    0.12       0
Bank Sta=4994.1,5002.7
Exp/Cntr=0.3,0.1

Type RM Length L Ch R = 1,1450,448,448,448
BEGIN DESCRIPTION:
LITTLE LLANO 056 3.0
END DESCRIPTION:
XS GIS Cut Line= 3
      2836755.69     10281753.12      2836649.75     10281510.00
      2836705.68     10281203.15
#Sta/Elev= 30
  4734.8 1108.70  4775.7 1105.50  4811.2 1102.77  4842.9 1096.39  4848.4 1095.87
  4884.9 1095.36  4918.7 1094.62  4924.1 1095.49  4931.2 1095.46  4947.6 1092.84
  4953.0 1094.09  4971.0 1092.40  4976.4 1094.03  4985.7 1093.18  4990.1 1091.94
  4990.6 1091.44  4998.8 1091.94  5008.6 1092.69  5017.2 1095.56  5027.3 1097.57
  5047.7 1099.24  5068.0 1102.36  5129.0 1103.54  5173.6 1103.36  5200.1 1104.94
  5232.0 1105.10  5285.3 1107.84  5291.6 1109.77  5301.8 1111.26  5311.9 1111.26
#Mann=5,-1,0
  4734.8    0.05       0  4775.7    0.12       0  4884.9    0.05       0
  4990.1    0.05       0  4998.8    0.05       0
Bank Sta=4990.1,4998.8
Exp/Cntr=0.3,0.1

Type RM Length L Ch R = 1,1002,463,463,463
BEGIN DESCRIPTION:
LITTLE LLANO 056 2.0
END DESCRIPTION:
XS GIS Cut Line= 3
      2836955.71     10281703.09      2837041.75     10281612.00
      2836755.70     10281203.13
#Sta/Elev= 30
  4874.7 1105.97  4878.1 1105.97  4938.4 1096.37  4952.5 1094.71  4973.6 1093.56
  4980.9 1092.38  4987.7 1092.43  4994.9 1090.56  4995.4 1090.06  5003.6 1090.56
  5024.2 1092.00  5033.0 1093.53  5060.0 1094.84  5068.7 1097.84  5074.8 1097.61
  5083.5 1100.17  5089.6 1099.74  5104.5 1101.51  5146.3 1102.19  5182.1 1101.59
  5218.3 1102.34  5283.2 1102.35  5312.9 1101.53  5347.7 1102.03  5426.2 1104.25
  5455.9 1105.70  5459.8 1106.91  5462.4 1107.71  5476.8 1108.03  5499.0 1111.57
#Mann=5,-1,0
  4874.7    0.05       0  4994.9    0.05       0  5003.6    0.05       0
  5347.7    0.12       0  5459.8    0.05       0
Bank Sta=4994.9,5003.6
Exp/Cntr=0.3,0.1

Type RM Length L Ch R = 1,539,0,0,0
BEGIN DESCRIPTION:
LITTLE LLANO 056 1.0
END DESCRIPTION:
XS GIS Cut Line= 3
      2837505.68     10281703.11      2837495.50     10281524.00
      2837105.67     10281103.09
#Sta/Elev= 30
  4820.6 1103.75  4830.6 1103.06  4880.7 1101.48  4900.7 1100.11  4907.2 1099.09
  4920.8 1098.14  4940.8 1095.50  4960.8 1091.51  4970.8 1089.02  4993.5 1087.65
  4994.0 1087.15  5001.9 1087.15  5002.4 1087.65  5014.8 1087.77  5021.7 1088.66
  5028.5 1088.95  5035.9 1090.91  5042.7 1091.93  5050.1 1094.97  5064.3 1096.81
  5092.6 1098.09  5141.9 1098.12  5163.5 1097.55  5233.8 1097.58  5255.3 1097.15
  5262.1 1097.53  5333.0 1097.44  5382.9 1098.49  5509.9 1103.38  5573.7 1106.32
#Mann=3,-1,0
  4820.6    0.05       0  4993.5    0.03       0  5002.4    0.05       0
Bank Sta=4993.5,5002.4
Exp/Cntr=0.3,0.1

Chan Stop Cuts=-1