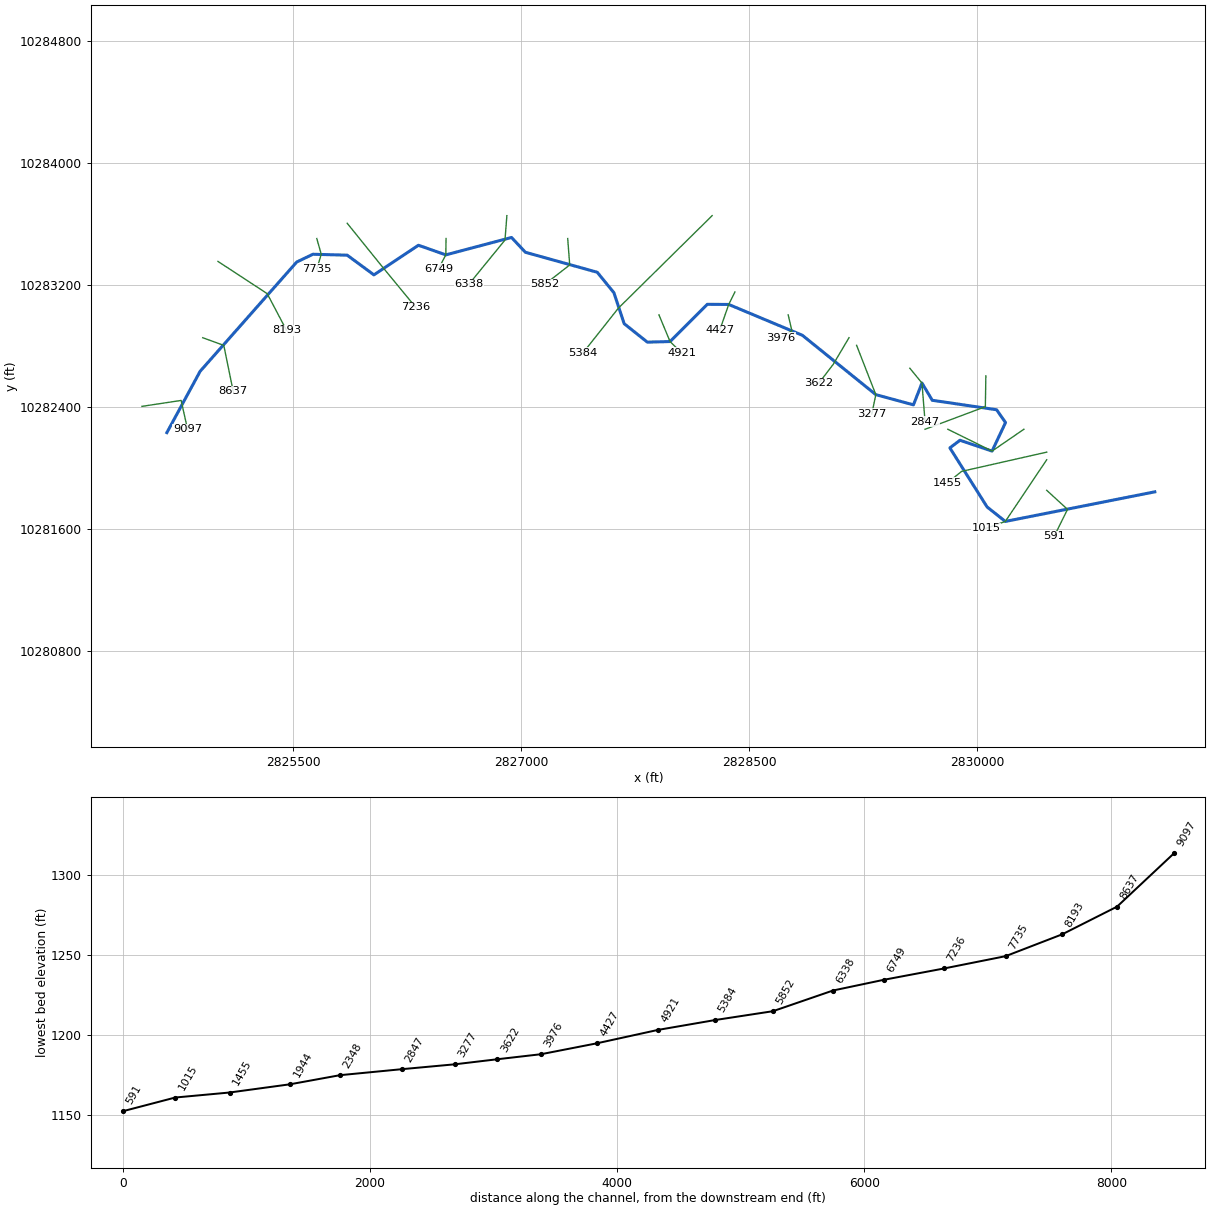
--- LITTLE LLANO 057.prj (project) ---

Proj Title=LITTLE LLANO 057 Base Level Engineering
Current Plan=p01
Default Exp/Contr=0.3,0.1
English Units
Geom File=g01
Flow File=f01
Plan File=p01
BEGIN DESCRIPTION:
LITTLE LLANO 057
END DESCRIPTION:

--- LITTLE LLANO 057.p01 (plan) ---

Plan Title=Multiple Run
Short Identifier=Multiple
Geom File=g01
Flow File=f01
Subcritical Flow
K Sum by GR= 0
Std Step Tol= 0.01
Critical Tol= 0.01
Num of Std Step Trials= 20
Max Error Tol= 0.3
Flow Tol Ratio= 0.001
Split Flow NTrial= 30
Split Flow Tol= 0.02
Split Flow Ratio= 0.02
Log Output Level= 0
Friction Slope Method= 1
Unsteady Friction Slope Method= 2
Unsteady Bridges Friction Slope Method= 1
Parabolic Critical Depth
Global Vel Dist=  1 , 1 , 1
Global Log Level= 0
CheckData=True
Encroach Param= -1, 0, 0, 0
BEGIN DESCRIPTION:
Multiple Run
END DESCRIPTION:

--- LITTLE LLANO 057.f01 (steady flow) ---

Flow Title=Multiple
Number of Profiles=7
Profile Names=10-year,25-year,50-year,1pct_min,100-year,1pct_plu,500-year
River Rch & RM= LITTLE LLANO 057,Reach-1,9097
      70     131     203     105     317     958     834
River Rch & RM= LITTLE LLANO 057,Reach-1,2348
      77     150     235     123     371    1120     988
Boundary for River Rch & Prof#=LITTLE LLANO 057,Reach-1,1
Up Type=0
Dn Type=3
Dn Slope=0.005
Boundary for River Rch & Prof#=LITTLE LLANO 057,Reach-1,2
Up Type=0
Dn Type=3
Dn Slope=0.005
Boundary for River Rch & Prof#=LITTLE LLANO 057,Reach-1,3
Up Type=0
Dn Type=3
Dn Slope=0.005
Boundary for River Rch & Prof#=LITTLE LLANO 057,Reach-1,4
Up Type=0
Dn Type=3
Dn Slope=0.005
Boundary for River Rch & Prof#=LITTLE LLANO 057,Reach-1,5
Up Type=0
Dn Type=3
Dn Slope=0.005
Boundary for River Rch & Prof#=LITTLE LLANO 057,Reach-1,6
Up Type=0
Dn Type=3
Dn Slope=0.005
Boundary for River Rch & Prof#=LITTLE LLANO 057,Reach-1,7
Up Type=0
Dn Type=3
Dn Slope=0.005

--- LITTLE LLANO 057.g01 (geometry) ---

Geom Title=Existing Conditions

River Reach=LITTLE LLANO 057,Reach-1
Reach XY= 30
      2824669.75     10282231.00      2824888.50     10282633.00
      2825523.50     10283349.00      2825630.25     10283400.00
      2825855.50     10283394.00      2826031.25     10283265.00
      2826324.25     10283459.00      2826504.00     10283396.00
      2826936.25     10283510.00      2827027.50     10283413.00
      2827500.00     10283282.00      2827609.50     10283148.00
      2827677.00     10282945.00      2827829.50     10282824.00
      2827978.75     10282828.00      2828224.00     10283072.00
      2828364.75     10283071.00      2828849.00     10282869.00
      2829332.00     10282480.00      2829579.50     10282413.00
      2829635.50     10282556.00      2829703.25     10282443.00
      2830126.25     10282381.00      2830185.00     10282297.00
      2830096.50     10282110.00      2829885.50     10282181.00
      2829819.00     10282131.00      2830063.75     10281744.00
      2830183.75     10281649.00      2831166.50     10281843.00

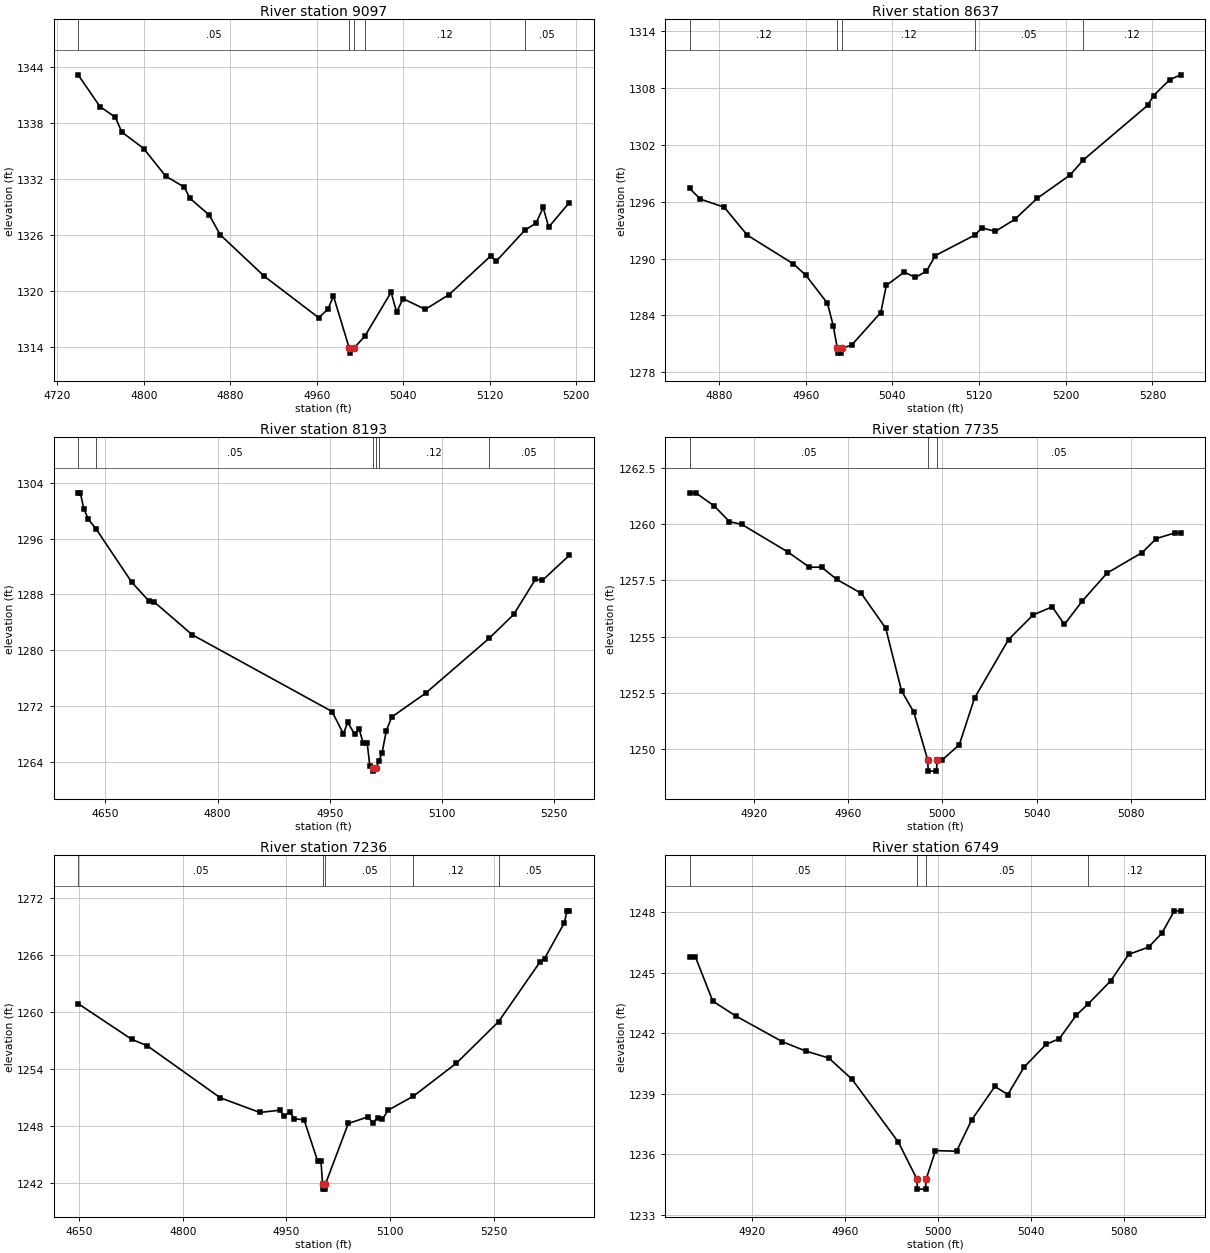
Type RM Length L Ch R = 1,9097,460,460,460
BEGIN DESCRIPTION:
LITTLE LLANO 057 20.0
END DESCRIPTION:
XS GIS Cut Line= 3
      2824505.72     10282403.12      2824763.50     10282442.00
      2824805.68     10282253.15
#Sta/Elev= 30
  4739.3 1343.14  4759.5 1339.74  4773.7 1338.59  4779.7 1337.01  4799.9 1335.24
  4820.2 1332.29  4837.6 1331.09  4842.6 1329.91  4860.6 1328.10  4870.7 1325.99
  4911.6 1321.53  4961.8 1317.09  4970.4 1318.03  4975.4 1319.42  4990.1 1313.80
  4990.3 1313.30  4994.1 1313.80  5004.5 1315.13  5028.7 1319.83  5033.8 1317.69
  5039.8 1319.14  5060.3 1317.99  5082.4 1319.58  5120.7 1323.71  5125.8 1323.14
  5152.2 1326.46  5162.8 1327.25  5169.3 1328.92  5174.4 1326.81  5193.5 1329.44
#Mann=5,-1,0
  4739.3    0.05       0  4990.1    0.05       0  4994.1    0.05       0
  5004.5    0.12       0  5152.2    0.05       0
Bank Sta=4990.1,4994.1
Exp/Cntr=0.3,0.1

Type RM Length L Ch R = 1,8637,444,444,444
BEGIN DESCRIPTION:
LITTLE LLANO 057 19.0
END DESCRIPTION:
XS GIS Cut Line= 3
      2824905.70     10282853.11      2825044.00     10282803.00
      2825105.69     10282503.08
#Sta/Elev= 30
  4852.9 1297.40  4862.9 1296.27  4884.8 1295.42  4906.1 1292.47  4948.6 1289.44
  4960.1 1288.24  4980.1 1285.27  4985.4 1282.92  4989.2 1280.51  4989.4 1280.01
  4992.9 1280.01  4993.2 1280.51  5002.5 1280.87  5029.3 1284.30  5034.4 1287.16
  5050.9 1288.57  5061.1 1288.01  5071.4 1288.65  5079.6 1290.31  5116.6 1292.51
  5122.4 1293.24  5135.1 1292.87  5153.0 1294.14  5173.4 1296.34  5204.1 1298.83
  5216.0 1300.39  5275.5 1306.17  5281.0 1307.21  5296.0 1308.89  5306.2 1309.40
#Mann=5,-1,0
  4852.9    0.12       0  4989.2    0.07       0  4993.2    0.12       0
  5116.6    0.05       0  5216.0    0.12       0
Bank Sta=4989.2,4993.2
Exp/Cntr=0.3,0.1

Type RM Length L Ch R = 1,8193,458,458,458
BEGIN DESCRIPTION:
LITTLE LLANO 057 18.0
END DESCRIPTION:
XS GIS Cut Line= 3
      2825005.65     10283353.14      2825329.50     10283142.00
      2825455.70     10282903.08
#Sta/Elev= 30
  4613.4 1302.56  4616.4 1302.56  4621.0 1300.29  4627.0 1298.80  4637.4 1297.39
  4685.1 1289.76  4708.6 1287.00  4714.5 1286.99  4765.9 1282.24  4952.9 1271.24
  4968.1 1268.05  4974.0 1269.68  4983.2 1267.96  4989.1 1268.71  4994.7 1266.70
  5000.0 1266.70  5003.5 1263.37  5008.1 1263.20  5008.3 1262.70  5012.1 1263.20
  5015.4 1264.10  5019.8 1265.31  5025.5 1268.48  5032.7 1270.45  5077.9 1273.85
  5162.8 1281.70  5195.9 1285.14  5224.9 1290.18  5234.3 1290.03  5270.2 1293.61
#Mann=6,-1,0
  4613.4    0.12       0  4637.4    0.05       0  5008.1    0.03       0
  5012.1    0.05       0  5015.4    0.12       0  5162.8    0.05       0
Bank Sta=5008.1,5012.1
Exp/Cntr=0.3,0.1

Type RM Length L Ch R = 1,7735,499,499,499
BEGIN DESCRIPTION:
LITTLE LLANO 057 17.0
END DESCRIPTION:
XS GIS Cut Line= 3
      2825655.68     10283503.11      2825685.00     10283400.00
      2825655.69     10283303.14
#Sta/Elev= 30
  4892.8 1261.39  4895.4 1261.39  4903.2 1260.81  4909.7 1260.11  4914.9 1259.99
  4934.4 1258.77  4943.6 1258.09  4948.8 1258.09  4955.2 1257.55  4965.6 1256.93
  4976.0 1255.38  4982.7 1252.60  4987.9 1251.66  4993.8 1249.54  4994.0 1249.04
  4997.5 1249.04  4997.8 1249.54  5000.0 1249.54  5007.2 1250.21  5013.7 1252.29
  5028.1 1254.88  5038.5 1255.97  5046.6 1256.33  5051.8 1255.55  5059.4 1256.59
  5069.9 1257.83  5084.8 1258.74  5090.8 1259.36  5098.6 1259.61  5101.2 1259.61
#Mann=3,-1,0
  4892.8    0.05       0  4993.8    0.05       0  4997.8    0.05       0
Bank Sta=4993.8,4997.8
Exp/Cntr=0.3,0.1

Type RM Length L Ch R = 1,7236,487,487,487
BEGIN DESCRIPTION:
LITTLE LLANO 057 16.0
END DESCRIPTION:
XS GIS Cut Line= 3
      2825855.66     10283603.14      2826076.75     10283330.00
      2826305.70     10283053.09
#Sta/Elev= 30
  4648.6 1260.87  4726.2 1257.11  4748.5 1256.44  4854.5 1250.95  4911.6 1249.41
  4940.4 1249.65  4946.8 1249.01  4954.8 1249.48  4961.2 1248.75  4975.6 1248.63
  4995.2 1244.28  5000.0 1244.28  5002.3 1241.84  5002.6 1241.34  5006.1 1241.34
  5006.3 1241.84  5039.5 1248.25  5068.1 1248.95  5074.6 1248.34  5082.5 1248.85
  5089.0 1248.68  5096.8 1249.64  5133.8 1251.13  5195.8 1254.59  5256.9 1258.97
  5317.0 1265.27  5323.4 1265.61  5352.1 1269.38  5356.0 1270.64  5359.3 1270.64
#Mann=5,-1,0
  4648.6    0.05       0  5002.3    0.05       0  5006.3    0.05       0
  5133.8    0.12       0  5256.9    0.05       0
Bank Sta=5002.3,5006.3
Exp/Cntr=0.3,0.1

Type RM Length L Ch R = 1,6749,411,411,411
BEGIN DESCRIPTION:
LITTLE LLANO 057 15.0
END DESCRIPTION:
XS GIS Cut Line= 3
      2826505.68     10283503.09      2826504.00     10283396.00
      2826455.69     10283303.11
#Sta/Elev= 29
  4892.9 1245.77  4895.4 1245.77  4902.9 1243.58  4912.9 1242.84  4932.9 1241.57
  4942.9 1241.11  4952.9 1240.76  4962.9 1239.71  4982.9 1236.59  4990.9 1234.76
  4991.1 1234.26  4994.6 1234.26  4994.9 1234.76  4998.9 1236.17  5008.0 1236.14
  5014.5 1237.69  5024.5 1239.35  5030.1 1238.95  5037.1 1240.31  5046.6 1241.44
  5052.3 1241.72  5059.6 1242.88  5064.8 1243.45  5074.4 1244.58  5082.2 1245.90
  5090.8 1246.26  5096.5 1246.95  5101.9 1248.06  5104.7 1248.06
#Mann=4,-1,0
  4892.9    0.05       0  4990.9    0.03       0  4994.9    0.05       0
  5064.8    0.12       0
Bank Sta=4990.9,4994.9
Exp/Cntr=0.3,0.1

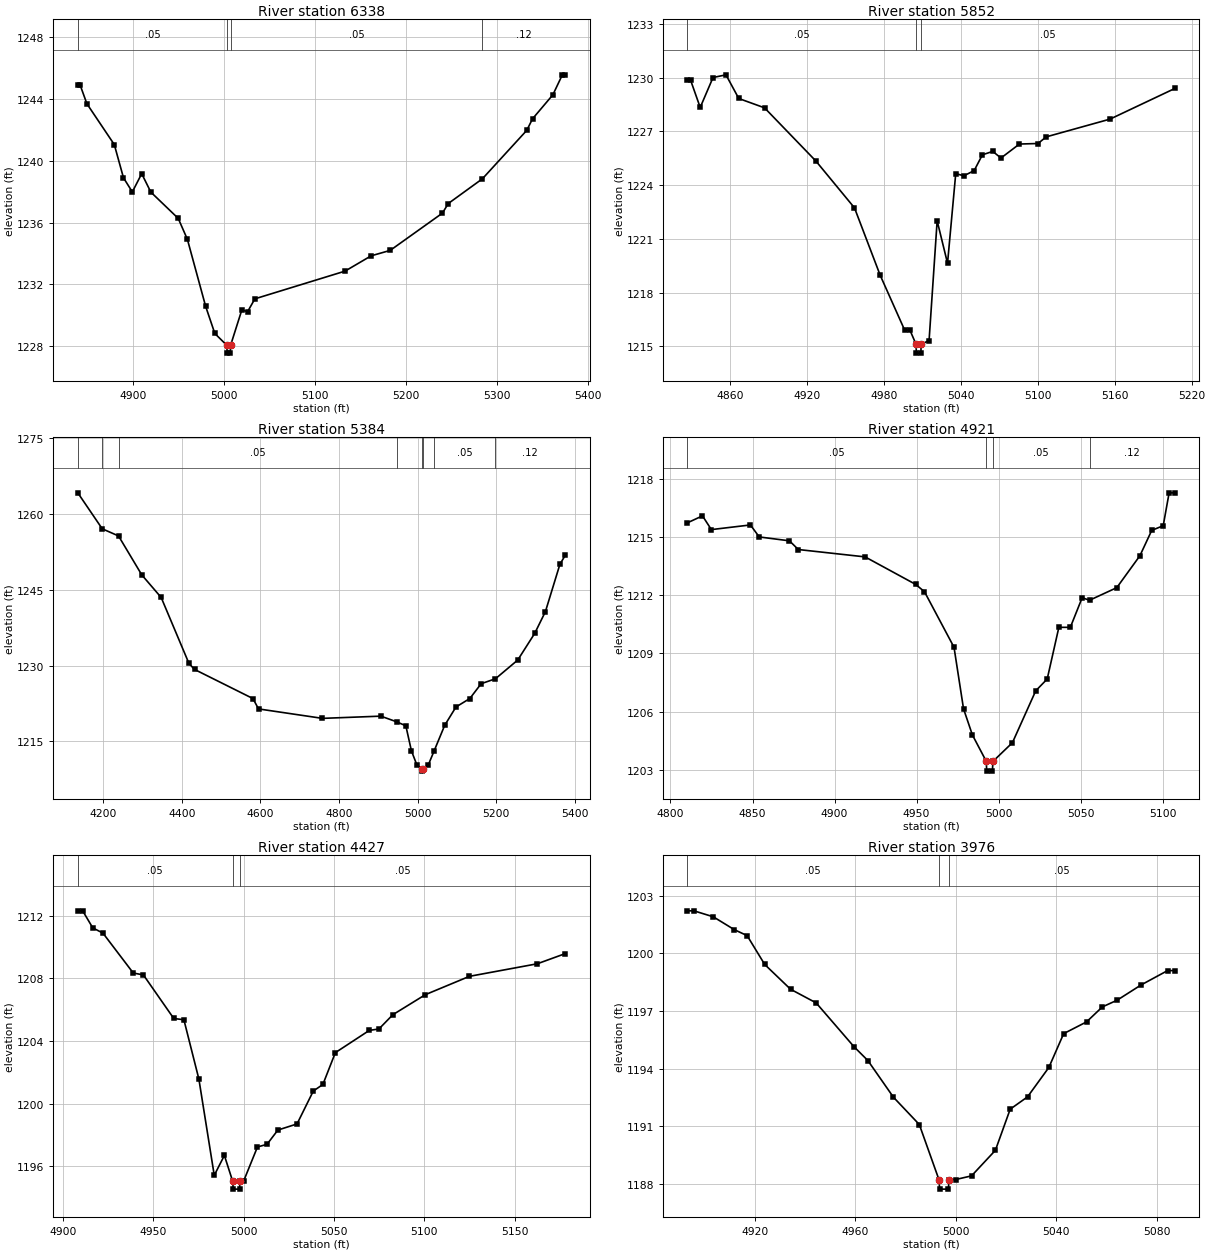
Type RM Length L Ch R = 1,6338,486,486,486
BEGIN DESCRIPTION:
LITTLE LLANO 057 14.0
END DESCRIPTION:
XS GIS Cut Line= 3
      2826905.68     10283653.12      2826893.25     10283493.00
      2826655.68     10283203.11
#Sta/Elev= 30
  4839.4 1244.90  4841.9 1244.90  4849.4 1243.68  4879.5 1241.04  4889.6 1238.89
  4899.3 1237.98  4909.6 1239.16  4919.6 1237.97  4949.7 1236.27  4959.8 1234.91
  4979.8 1230.59  4989.9 1228.83  5003.2 1228.06  5003.4 1227.56  5006.9 1227.56
  5007.2 1228.06  5019.5 1230.34  5026.0 1230.25  5033.9 1231.07  5132.9 1232.86
  5161.6 1233.85  5182.5 1234.20  5239.9 1236.61  5246.3 1237.23  5283.8 1238.83
  5332.5 1241.96  5338.9 1242.71  5361.2 1244.26  5371.6 1245.55  5374.8 1245.55
#Mann=4,-1,0
  4839.4    0.05       0  5003.2    0.03       0  5007.2    0.05       0
  5283.8    0.12       0
Bank Sta=5003.2,5007.2
Exp/Cntr=0.3,0.1

Type RM Length L Ch R = 1,5852,468,468,468
BEGIN DESCRIPTION:
LITTLE LLANO 057 13.0
END DESCRIPTION:
XS GIS Cut Line= 3
      2827305.69     10283503.09      2827319.00     10283330.00
      2827155.70     10283203.12
#Sta/Elev= 30
  4826.4 1229.85  4828.9 1229.85  4836.4 1228.33  4846.4 1230.00  4856.5 1230.15
  4866.5 1228.83  4886.6 1228.31  4926.7 1225.34  4956.8 1222.73  4976.8 1218.98
  4995.9 1215.92  5000.0 1215.92  5004.8 1215.13  5005.1 1214.63  5008.6 1214.63
  5008.8 1215.13  5015.0 1215.33  5021.3 1222.01  5029.4 1219.64  5035.8 1224.64
  5042.2 1224.52  5050.2 1224.81  5056.6 1225.69  5064.7 1225.88  5071.1 1225.51
  5085.5 1226.29  5100.0 1226.32  5106.4 1226.69  5156.2 1227.68  5206.8 1229.39
#Mann=3,-1,0
  4826.4    0.05       0  5004.8    0.03       0  5008.8    0.05       0
Bank Sta=5004.8,5008.8
Exp/Cntr=0.3,0.1

Type RM Length L Ch R = 1,5384,463,463,463
BEGIN DESCRIPTION:
LITTLE LLANO 057 12.0
END DESCRIPTION:
XS GIS Cut Line= 3
      2828255.68     10283653.11      2827639.25     10283047.00
      2827405.68     10282753.11
#Sta/Elev= 30
  4135.5 1264.17  4197.7 1257.05  4239.1 1255.64  4298.2 1247.94  4347.6 1243.46
  4418.3 1230.40  4432.5 1229.22  4581.0 1223.46  4595.2 1221.41  4757.8 1219.54
  4906.3 1219.98  4946.2 1218.87  4969.9 1218.07  4984.1 1213.12  4998.2 1210.28
  5010.6 1209.60  5010.8 1209.10  5014.6 1209.60  5027.0 1210.32  5041.3 1213.00
  5068.8 1218.17  5097.4 1221.79  5132.7 1223.47  5161.5 1226.40  5197.9 1227.38
  5254.5 1231.08  5297.7 1236.36  5324.9 1240.66  5361.8 1250.03  5375.4 1251.81
#Mann=8,-1,0
  4135.5    0.05       0  4197.7    0.12       0  4239.1    0.05       0
  4946.2    0.12       0  5010.6    0.07       0  5014.6    0.12       0
  5041.3    0.05       0  5197.9    0.12       0
Bank Sta=5010.6,5014.6
Exp/Cntr=0.3,0.1

Type RM Length L Ch R = 1,4921,494,494,494
BEGIN DESCRIPTION:
LITTLE LLANO 057 11.0
END DESCRIPTION:
XS GIS Cut Line= 3
      2827905.70     10283003.07      2827978.75     10282828.00
      2828055.71     10282753.09
#Sta/Elev= 30
  4810.3 1215.75  4819.5 1216.11  4824.9 1215.40  4848.7 1215.64  4854.1 1215.02
  4872.5 1214.82  4877.9 1214.37  4918.6 1213.99  4949.4 1212.57  4954.8 1212.19
  4972.8 1209.32  4978.6 1206.14  4984.0 1204.79  4992.5 1203.42  4992.7 1202.92
  4996.2 1202.92  4996.5 1203.42  5008.4 1204.39  5022.6 1207.07  5029.6 1207.68
  5036.7 1210.35  5043.7 1210.35  5050.9 1211.88  5055.4 1211.75  5072.0 1212.40
  5086.1 1214.05  5093.3 1215.36  5100.3 1215.60  5103.9 1217.30  5107.4 1217.30
#Mann=4,-1,0
  4810.3    0.05       0  4992.5    0.03       0  4996.5    0.05       0
  5055.4    0.12       0
Bank Sta=4992.5,4996.5
Exp/Cntr=0.3,0.1

Type RM Length L Ch R = 1,4427,451,451,451
BEGIN DESCRIPTION:
LITTLE LLANO 057 10.0
END DESCRIPTION:
XS GIS Cut Line= 3
      2828405.66     10283153.07      2828364.75     10283071.00
      2828305.68     10282903.09
#Sta/Elev= 30
  4908.3 1212.31  4911.0 1212.31  4916.6 1211.22  4922.2 1210.89  4939.0 1208.34
  4944.6 1208.22  4961.4 1205.44  4967.0 1205.36  4975.3 1201.57  4983.8 1195.43
  4989.4 1196.70  4994.0 1195.05  4994.3 1194.55  4997.8 1194.55  4998.0 1195.05
  5000.0 1195.05  5007.7 1197.24  5013.0 1197.41  5019.0 1198.32  5029.6 1198.71
  5038.6 1200.81  5043.9 1201.23  5050.8 1203.26  5069.6 1204.68  5074.9 1204.77
  5082.6 1205.68  5100.6 1206.96  5125.0 1208.13  5162.5 1208.93  5178.0 1209.58
#Mann=3,-1,0
  4908.3    0.05       0  4994.0    0.03       0  4998.0    0.05       0
Bank Sta=4994,4998
Exp/Cntr=0.3,0.1

Type RM Length L Ch R = 1,3976,354,354,354
BEGIN DESCRIPTION:
LITTLE LLANO 057 9.0
END DESCRIPTION:
XS GIS Cut Line= 3
      2828755.69     10283003.10      2828780.00     10282899.00
      2828705.72     10282853.13
#Sta/Elev= 29
  4893.1 1202.22  4895.7 1202.22  4903.4 1201.91  4911.8 1201.24  4916.9 1200.93
  4923.9 1199.43  4934.2 1198.14  4944.4 1197.43  4959.4 1195.16  4965.0 1194.43
  4975.2 1192.52  4985.5 1191.10  4993.3 1188.24  4993.6 1187.74  4997.1 1187.74
  4997.3 1188.24  5000.0 1188.24  5006.3 1188.43  5015.8 1189.76  5021.7 1191.90
  5028.6 1192.54  5037.1 1194.07  5043.0 1195.83  5052.1 1196.44  5058.4 1197.22
  5064.3 1197.57  5073.8 1198.36  5084.4 1199.11  5087.3 1199.11
#Mann=3,-1,0
  4893.1    0.05       0  4993.3    0.03       0  4997.3    0.05       0
Bank Sta=4993.3,4997.3
Exp/Cntr=0.3,0.1

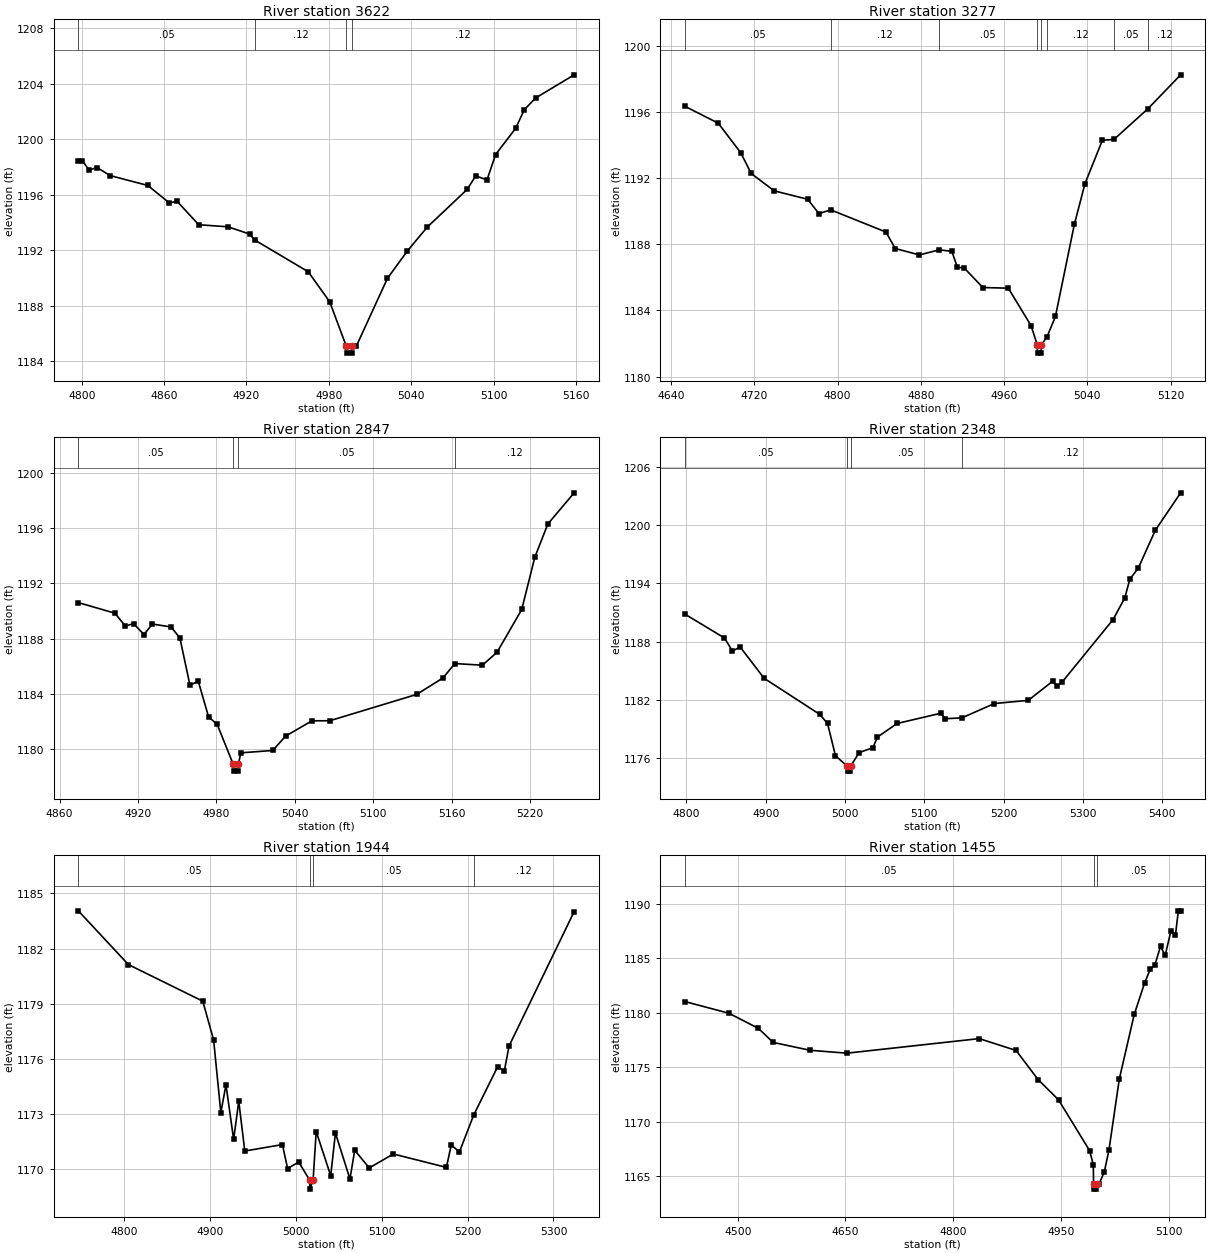
Type RM Length L Ch R = 1,3622,345,345,345
BEGIN DESCRIPTION:
LITTLE LLANO 057 8.0
END DESCRIPTION:
XS GIS Cut Line= 3
      2829155.68     10282853.10      2829052.25     10282679.00
      2828955.66     10282553.08
#Sta/Elev= 30
  4797.5 1198.46  4800.4 1198.46  4805.3 1197.78  4811.1 1197.96  4820.7 1197.38
  4848.1 1196.67  4863.7 1195.42  4869.5 1195.52  4885.2 1193.84  4906.6 1193.69
  4922.2 1193.17  4926.0 1192.74  4965.0 1190.45  4980.6 1188.29  4992.7 1185.09
  4993.0 1184.59  4996.5 1184.59  4996.7 1185.09  5000.0 1185.09  5022.7 1189.98
  5037.2 1191.95  5051.7 1193.67  5080.7 1196.38  5087.0 1197.36  5095.2 1197.07
  5101.5 1198.90  5116.1 1200.79  5122.4 1202.13  5130.6 1202.97  5158.7 1204.64
#Mann=4,-1,0
  4797.5    0.05       0  4926.0    0.12       0  4992.7    0.07       0
  4996.7    0.12       0
Bank Sta=4992.7,4996.7
Exp/Cntr=0.3,0.1

Type RM Length L Ch R = 1,3277,430,430,430
BEGIN DESCRIPTION:
LITTLE LLANO 057 7.0
END DESCRIPTION:
XS GIS Cut Line= 3
      2829205.69     10282803.09      2829332.00     10282480.00
      2829305.68     10282353.10
#Sta/Elev= 30
  4653.1 1196.36  4685.3 1195.33  4706.8 1193.55  4716.9 1192.29  4739.0 1191.24
  4771.2 1190.73  4782.0 1189.86  4793.3 1190.09  4846.3 1188.75  4855.4 1187.75
  4878.6 1187.36  4897.6 1187.67  4909.7 1187.58  4915.1 1186.61  4921.5 1186.58
  4939.5 1185.39  4964.0 1185.35  4985.9 1183.08  4991.8 1181.92  4992.1 1181.42
  4995.6 1181.42  4995.8 1181.92  5001.3 1182.42  5009.3 1183.64  5027.5 1189.22
  5037.7 1191.68  5054.4 1194.30  5065.5 1194.35  5098.4 1196.22  5129.6 1198.26
#Mann=8,-1,0
  4653.1    0.05       0  4793.3    0.12       0  4897.6    0.05       0
  4991.8    0.03       0  4995.8    0.05       0  5001.3    0.12       0
  5065.5    0.05       0  5098.4    0.12       0
Bank Sta=4991.8,4995.8
Exp/Cntr=0.3,0.1

Type RM Length L Ch R = 1,2847,499,499,499
BEGIN DESCRIPTION:
LITTLE LLANO 057 6.0
END DESCRIPTION:
XS GIS Cut Line= 3
      2829555.69     10282653.11      2829635.50     10282556.00
      2829655.68     10282303.10
#Sta/Elev= 30
  4874.3 1190.61  4902.3 1189.84  4910.2 1188.91  4916.6 1189.08  4924.5 1188.29
  4931.0 1189.05  4945.3 1188.84  4952.0 1188.04  4959.7 1184.62  4966.1 1184.89
  4974.0 1182.29  4980.5 1181.77  4992.8 1178.86  4993.1 1178.36  4996.6 1178.36
  4996.8 1178.86  4998.6 1179.69  5023.0 1179.86  5033.0 1180.91  5053.1 1182.02
  5066.6 1182.02  5133.3 1183.94  5153.4 1185.14  5162.4 1186.18  5183.5 1186.06
  5194.7 1187.00  5213.6 1190.11  5223.6 1193.91  5233.6 1196.33  5253.7 1198.59
#Mann=4,-1,0
  4874.3    0.05       0  4992.8    0.03       0  4996.8    0.05       0
  5162.4    0.12       0
Bank Sta=4992.8,4996.8
Exp/Cntr=0.3,0.1

Type RM Length L Ch R = 1,2348,404,404,404
BEGIN DESCRIPTION:
LITTLE LLANO 057 5.0
END DESCRIPTION:
XS GIS Cut Line= 3
      2830055.68     10282603.07      2830052.25     10282401.00
      2829655.73     10282253.13
#Sta/Elev= 30
  4797.9 1190.84  4847.9 1188.37  4857.9 1187.04  4867.9 1187.42  4897.9 1184.21
  4967.9 1180.49  4977.9 1179.55  4987.9 1176.21  5002.9 1175.12  5003.2 1174.62
  5006.8 1174.62  5007.0 1175.12  5017.7 1176.53  5035.3 1177.05  5040.6 1178.12
  5065.6 1179.54  5120.9 1180.60  5126.2 1180.03  5147.3 1180.12  5188.4 1181.60
  5231.1 1181.93  5261.8 1183.90  5267.2 1183.37  5273.8 1183.82  5337.9 1190.26
  5352.8 1192.51  5359.2 1194.45  5369.9 1195.60  5391.2 1199.48  5423.2 1203.36
#Mann=4,-1,0
  4797.9    0.05       0  5002.9    0.03       0  5007.0    0.05       0
  5147.3    0.12       0
Bank Sta=5002.9,5007
Exp/Cntr=0.3,0.1

Type RM Length L Ch R = 1,1944,489,489,489
BEGIN DESCRIPTION:
LITTLE LLANO 057 4.0
END DESCRIPTION:
XS GIS Cut Line= 3
      2830305.72     10282253.14      2830096.50     10282110.00
      2829805.70     10282253.10
#Sta/Elev= 30
  4746.5 1184.05  4804.8 1181.13  4891.5 1179.14  4904.1 1177.03  4912.5 1173.09
  4918.5 1174.60  4927.4 1171.63  4933.4 1173.70  4940.4 1171.00  4984.2 1171.35
  4990.3 1170.05  5003.2 1170.40  5015.9 1169.43  5016.2 1168.93  5020.0 1169.43
  5023.6 1172.06  5040.5 1169.66  5046.0 1171.98  5062.9 1169.48  5068.5 1171.04
  5085.4 1170.08  5113.4 1170.84  5175.3 1170.11  5180.9 1171.33  5190.4 1170.95
  5207.3 1172.98  5235.0 1175.58  5242.7 1175.34  5248.3 1176.71  5324.1 1184.01
#Mann=4,-1,0
  4746.5    0.05       0  5015.9    0.05       0  5020.0    0.05       0
  5207.3    0.12       0
Bank Sta=5015.9,5020
Exp/Cntr=0.3,0.1

Type RM Length L Ch R = 1,1455,440,440,440
BEGIN DESCRIPTION:
LITTLE LLANO 057 3.0
END DESCRIPTION:
XS GIS Cut Line= 3
      2830455.67     10282103.11      2829896.00     10281977.00
      2829805.68     10281903.10
#Sta/Elev= 30
  4426.3 1181.04  4487.8 1179.96  4528.8 1178.57  4549.3 1177.28  4600.5 1176.56
  4651.8 1176.29  4836.3 1177.63  4887.6 1176.54  4918.3 1173.86  4946.7 1172.00
  4989.9 1167.34  4995.1 1166.04  4995.5 1164.29  4995.8 1163.79  4999.4 1163.79
  4999.6 1164.29  5003.4 1164.29  5010.5 1165.40  5016.9 1167.38  5031.3 1173.91
  5052.1 1179.85  5066.4 1182.72  5074.3 1184.00  5080.8 1184.39  5088.7 1186.11
  5095.2 1185.28  5103.1 1187.51  5109.5 1187.15  5113.5 1189.38  5116.7 1189.38
#Mann=3,-1,0
  4426.3    0.05       0  4995.5    0.05       0  4999.6    0.05       0
Bank Sta=4995.5,4999.6
Exp/Cntr=0.3,0.1

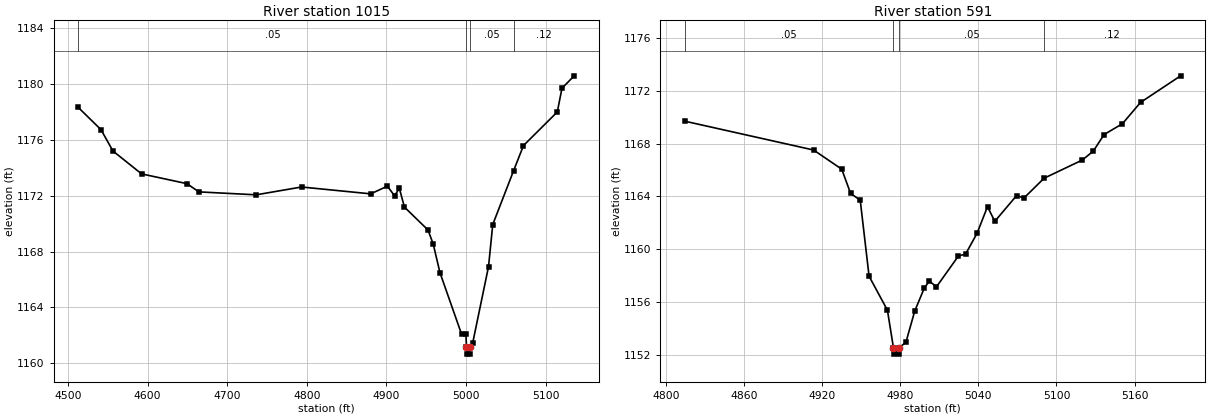
Type RM Length L Ch R = 1,1015,424,424,424
BEGIN DESCRIPTION:
LITTLE LLANO 057 2.0
END DESCRIPTION:
XS GIS Cut Line= 3
      2830455.69     10282053.12      2830183.75     10281649.00
      2830055.72     10281603.12
#Sta/Elev= 30
  4512.9 1178.33  4541.4 1176.74  4556.4 1175.21  4592.4 1173.57  4649.4 1172.87
  4664.4 1172.28  4736.4 1172.07  4793.4 1172.63  4880.3 1172.14  4901.3 1172.69
  4910.3 1172.00  4916.3 1172.54  4922.7 1171.19  4952.3 1169.55  4958.9 1168.54
  4967.3 1166.50  4994.5 1162.08  5000.0 1162.08  5000.7 1161.15  5001.0 1160.65
  5004.8 1160.65  5005.1 1161.15  5008.6 1161.48  5028.4 1166.93  5033.7 1169.94
  5059.9 1173.80  5072.3 1175.60  5114.8 1178.01  5120.7 1179.71  5136.0 1180.60
#Mann=4,-1,0
  4512.9    0.05       0  5000.7    0.03       0  5005.1    0.05       0
  5059.9    0.12       0
Bank Sta=5000.7,5005.1
Exp/Cntr=0.3,0.1

Type RM Length L Ch R = 1,591,0,0,0
BEGIN DESCRIPTION:
LITTLE LLANO 057 1.0
END DESCRIPTION:
XS GIS Cut Line= 3
      2830455.67     10281853.13      2830592.75     10281728.00
      2830505.67     10281553.08
#Sta/Elev= 30
  4814.4 1169.69  4913.4 1167.51  4935.0 1166.06  4941.8 1164.23  4949.2 1163.72
  4956.0 1157.97  4970.1 1155.40  4974.7 1152.58  4975.0 1152.08  4978.8 1152.08
  4979.2 1152.58  4984.3 1152.97  4991.1 1155.34  4998.5 1157.09  5002.3 1157.60
  5007.8 1157.17  5024.6 1159.49  5030.2 1159.65  5039.0 1161.22  5047.0 1163.23
  5052.6 1162.12  5069.4 1164.07  5075.0 1163.88  5090.5 1165.38  5119.8 1166.75
  5128.3 1167.43  5136.6 1168.68  5150.7 1169.50  5164.6 1171.11  5195.4 1173.12
#Mann=4,-1,0
  4814.4    0.05       0  4974.7    0.05       0  4979.2    0.05       0
  5090.5    0.12       0
Bank Sta=4974.7,4979.2
Exp/Cntr=0.3,0.1

Chan Stop Cuts=-1