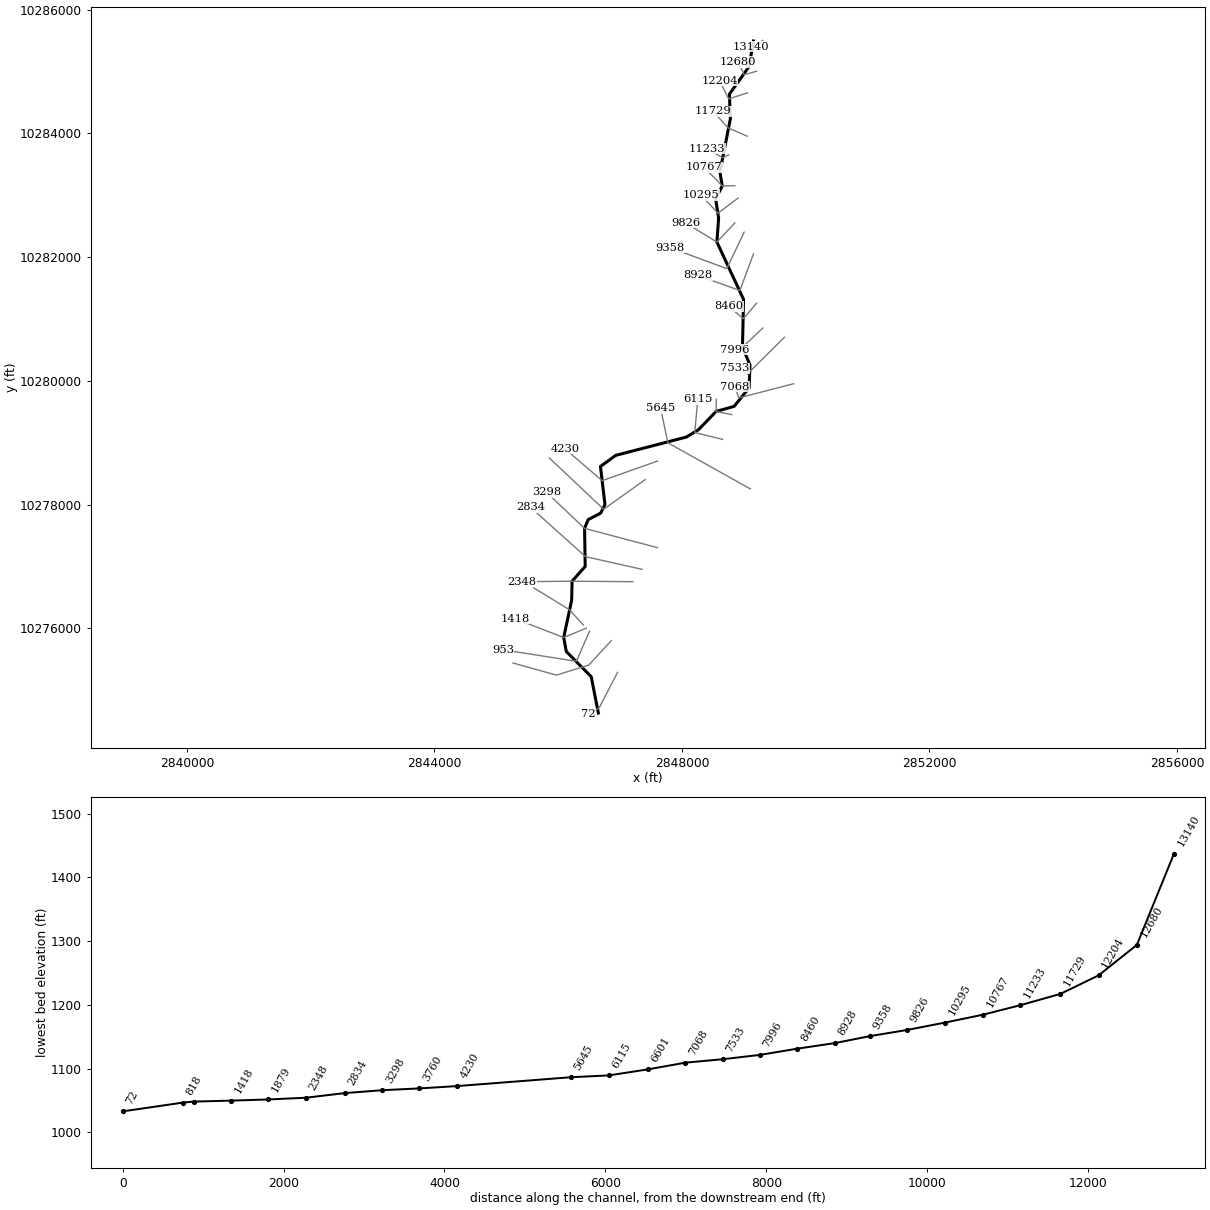
--- LITTLE LLANO 058.prj (project) ---

Proj Title=LITTLE LLANO 058 Base Level Engineering
Current Plan=p01
Default Exp/Contr=0.3,0.1
English Units
Geom File=g01
Flow File=f01
Plan File=p01
BEGIN DESCRIPTION:
LITTLE LLANO 058
END DESCRIPTION:

--- LITTLE LLANO 058.p01 (plan) ---

Plan Title=Multiple Run
Short Identifier=Multiple
Geom File=g01
Flow File=f01
Subcritical Flow
K Sum by GR= 0
Std Step Tol= 0.01
Critical Tol= 0.01
Num of Std Step Trials= 20
Max Error Tol= 0.3
Flow Tol Ratio= 0.001
Split Flow NTrial= 30
Split Flow Tol= 0.02
Split Flow Ratio= 0.02
Log Output Level= 0
Friction Slope Method= 1
Unsteady Friction Slope Method= 2
Unsteady Bridges Friction Slope Method= 1
Parabolic Critical Depth
Global Vel Dist=  1 , 1 , 1
Global Log Level= 0
CheckData=True
Encroach Param= -1, 0, 0, 0
BEGIN DESCRIPTION:
Multiple Run
END DESCRIPTION:

--- LITTLE LLANO 058.f01 (steady flow) ---

Flow Title=Multiple
Number of Profiles=7
Profile Names=10-year,25-year,50-year,1pct_min,100-year,1pct_plu,500-year
River Rch & RM= LITTLE LLANO 058,Reach-1,13140
      73     134     208     107     324     979     851
River Rch & RM= LITTLE LLANO 058,Reach-1,2348
      81     154     242     126     380    1147    1010
Boundary for River Rch & Prof#=LITTLE LLANO 058,Reach-1,1
Up Type=0
Dn Type=3
Dn Slope=0.005
Boundary for River Rch & Prof#=LITTLE LLANO 058,Reach-1,2
Up Type=0
Dn Type=3
Dn Slope=0.005
Boundary for River Rch & Prof#=LITTLE LLANO 058,Reach-1,3
Up Type=0
Dn Type=3
Dn Slope=0.005
Boundary for River Rch & Prof#=LITTLE LLANO 058,Reach-1,4
Up Type=0
Dn Type=3
Dn Slope=0.005
Boundary for River Rch & Prof#=LITTLE LLANO 058,Reach-1,5
Up Type=0
Dn Type=3
Dn Slope=0.005
Boundary for River Rch & Prof#=LITTLE LLANO 058,Reach-1,6
Up Type=0
Dn Type=3
Dn Slope=0.005
Boundary for River Rch & Prof#=LITTLE LLANO 058,Reach-1,7
Up Type=0
Dn Type=3
Dn Slope=0.005

--- LITTLE LLANO 058.g01 (geometry) ---

Geom Title=Existing Conditions

River Reach=LITTLE LLANO 058,Reach-1
Reach XY= 30
      2849154.75     10285493.00      2849085.25     10285080.00
      2848766.00     10284632.00      2848783.25     10284240.00
      2848613.25     10283375.00      2848651.25     10283150.00
      2848543.75     10282941.00      2848592.25     10282632.00
      2848564.50     10282243.00      2848995.00     10281316.00
      2848977.75     10280542.00      2849099.25     10280257.00
      2849085.25     10279886.00      2848842.25     10279587.00
      2848550.50     10279504.00      2848269.25     10279212.00
      2848071.50     10279091.00      2846929.00     10278795.00
      2846682.50     10278615.00      2846755.50     10278000.00
      2846686.00     10277861.00      2846484.50     10277757.00
      2846425.75     10277615.00      2846436.00     10277000.00
      2846224.25     10276761.00      2846217.25     10276455.00
      2846088.75     10275851.00      2846130.50     10275625.00
      2846533.50     10275217.00      2846648.50     10274630.00

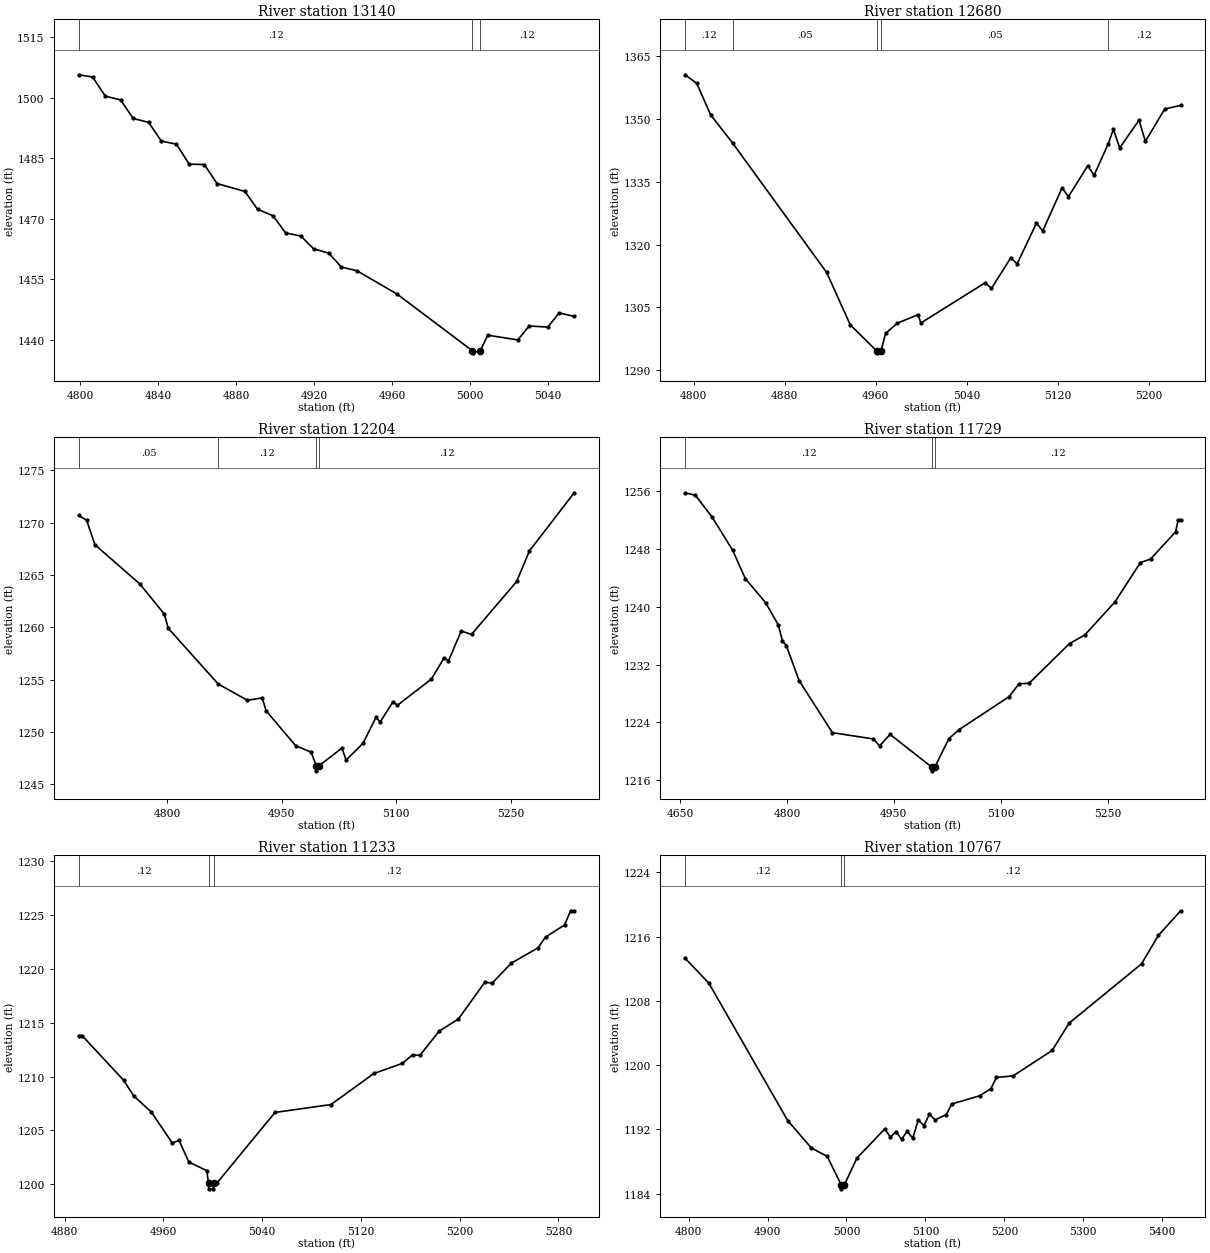
Type RM Length L Ch R = 1,13140,460,460,460
BEGIN DESCRIPTION:
LITTLE LLANO 058 26.0
END DESCRIPTION:
XS GIS Cut Line= 3
      2849305.72     10285503.14      2849151.25     10285375.00
      2849105.72     10285403.09
#Sta/Elev= 30
  4799.3 1505.73  4806.5 1505.18  4813.0 1500.41  4820.8 1499.51  4827.3 1494.89
  4835.2 1493.92  4841.7 1489.30  4849.5 1488.50  4856.0 1483.56  4863.8 1483.46
  4870.3 1478.74  4884.6 1476.79  4891.1 1472.35  4899.0 1470.75  4905.5 1466.49
  4913.3 1465.72  4919.8 1462.57  4927.6 1461.46  4934.1 1458.02  4942.0 1457.12
  4962.8 1451.27  5001.3 1437.24  5001.5 1436.74  5005.3 1437.24  5009.2 1441.11
  5024.6 1439.95  5030.4 1443.40  5040.0 1443.13  5045.8 1446.66  5053.5 1445.77
#Mann=3,-1,0
  4799.3    0.12       0  5001.3    0.07       0  5005.3    0.12       0
Bank Sta=5001.3,5005.3
Exp/Cntr=0.3,0.1

Type RM Length L Ch R = 1,12680,476,476,476
BEGIN DESCRIPTION:
LITTLE LLANO 058 25.0
END DESCRIPTION:
XS GIS Cut Line= 3
      2849205.65     10285003.10      2849005.50     10284948.00
      2848905.69     10285153.10
#Sta/Elev= 30
  4792.4 1360.56  4802.7 1358.49  4814.8 1351.02  4834.2 1344.25  4916.8 1313.37
  4937.6 1300.85  4960.7 1294.65  4961.0 1294.15  4964.7 1294.65  4968.7 1298.82
  4979.1 1301.24  4997.1 1303.26  4999.8 1301.29  5056.2 1310.88  5061.8 1309.54
  5078.8 1316.88  5084.3 1315.39  5101.3 1325.12  5106.9 1323.30  5123.9 1333.57
  5129.4 1331.44  5146.4 1338.81  5152.0 1336.58  5164.3 1343.99  5169.0 1347.53
  5174.5 1343.10  5191.5 1349.72  5197.1 1344.66  5214.1 1352.39  5228.1 1353.25
#Mann=5,-1,0
  4792.4    0.12       0  4834.2    0.05       0  4960.7    0.05       0
  4964.7    0.05       0  5164.3    0.12       0
Bank Sta=4960.7,4964.7
Exp/Cntr=0.3,0.1

Type RM Length L Ch R = 1,12204,475,475,475
BEGIN DESCRIPTION:
LITTLE LLANO 058 24.0
END DESCRIPTION:
XS GIS Cut Line= 3
      2849055.68     10284653.11      2848755.50     10284556.00
      2848605.71     10284853.07
#Sta/Elev= 30
  4684.5 1270.69  4695.0 1270.21  4705.8 1267.88  4764.5 1264.13  4796.5 1261.27
  4801.8 1259.89  4867.0 1254.58  4905.2 1253.02  4924.6 1253.25  4929.8 1252.01
  4968.3 1248.69  4988.6 1248.06  4995.3 1246.78  4995.5 1246.28  4999.3 1246.78
  5028.8 1248.45  5034.4 1247.31  5056.7 1248.93  5073.4 1251.38  5079.0 1250.95
  5095.7 1252.88  5101.3 1252.53  5146.0 1255.05  5162.7 1257.09  5168.3 1256.79
  5185.0 1259.64  5198.4 1259.31  5257.5 1264.37  5274.2 1267.29  5332.7 1272.84
#Mann=4,-1,0
  4684.5    0.05       0  4867.0    0.12       0  4995.3    0.07       0
  4999.3    0.12       0
Bank Sta=4995.3,4999.3
Exp/Cntr=0.3,0.1

Type RM Length L Ch R = 1,11729,496,496,496
BEGIN DESCRIPTION:
LITTLE LLANO 058 23.0
END DESCRIPTION:
XS GIS Cut Line= 3
      2849055.67     10283953.12      2848741.50     10284091.00
      2848505.67     10284353.13
#Sta/Elev= 30
  4656.9 1255.81  4671.3 1255.47  4694.7 1252.45  4723.5 1247.88  4741.4 1243.92
  4770.2 1240.54  4787.9 1237.46  4793.6 1235.27  4799.0 1234.63  4816.9 1229.78
  4863.7 1222.55  4921.3 1221.68  4929.9 1220.72  4944.7 1222.31  5003.4 1217.76
  5003.6 1217.26  5007.4 1217.76  5027.1 1221.70  5041.3 1222.96  5111.5 1227.52
  5125.7 1229.32  5139.9 1229.41  5196.7 1234.91  5218.1 1236.10  5260.3 1240.67
  5296.1 1246.13  5310.3 1246.62  5345.5 1250.39  5349.2 1252.07  5352.6 1252.07
#Mann=3,-1,0
  4656.9    0.12       0  5003.4    0.07       0  5007.4    0.12       0
Bank Sta=5003.4,5007.4
Exp/Cntr=0.3,0.1

Type RM Length L Ch R = 1,11233,466,466,466
BEGIN DESCRIPTION:
LITTLE LLANO 058 22.0
END DESCRIPTION:
XS GIS Cut Line= 3
      2848755.72     10283653.13      2848658.25     10283605.00
      2848405.68     10283753.12
#Sta/Elev= 30
  4891.3 1213.79  4894.1 1213.79  4927.8 1209.65  4935.9 1208.20  4950.2 1206.71
  4967.1 1203.85  4972.7 1204.07  4980.6 1202.07  4995.1 1201.28  4996.6 1200.09
  4996.9 1199.59  5000.4 1199.59  5000.6 1200.09  5003.1 1200.09  5050.4 1206.67
  5095.7 1207.40  5130.5 1210.28  5153.7 1211.22  5161.9 1212.02  5167.7 1211.95
  5183.4 1214.20  5199.0 1215.33  5220.5 1218.75  5226.3 1218.65  5242.0 1220.52
  5263.5 1221.92  5269.6 1222.93  5285.0 1224.04  5289.9 1225.36  5292.8 1225.36
#Mann=3,-1,0
  4891.3    0.12       0  4996.6    0.07       0  5000.6    0.12       0
Bank Sta=4996.6,5000.6
Exp/Cntr=0.3,0.1

Type RM Length L Ch R = 1,10767,472,472,472
BEGIN DESCRIPTION:
LITTLE LLANO 058 21.0
END DESCRIPTION:
XS GIS Cut Line= 3
      2848855.73     10283153.11      2848651.25     10283150.00
      2848355.66     10283453.14
#Sta/Elev= 30
  4795.5 1213.30  4825.5 1210.22  4925.6 1193.09  4955.6 1189.69  4975.6 1188.64
  4993.3 1185.11  4993.5 1184.61  4997.3 1185.11  5013.2 1188.43  5048.5 1192.07
  5055.7 1191.03  5062.7 1191.74  5069.8 1190.76  5076.8 1191.77  5084.0 1190.91
  5090.9 1193.17  5098.1 1192.49  5105.1 1193.88  5112.3 1193.18  5126.4 1193.85
  5133.4 1195.17  5168.8 1196.19  5183.0 1197.08  5190.0 1198.47  5211.3 1198.67
  5260.7 1201.84  5282.0 1205.22  5373.9 1212.61  5395.2 1216.15  5423.4 1219.21
#Mann=3,-1,0
  4795.5    0.12       0  4993.3    0.07       0  4997.3    0.12       0
Bank Sta=4993.3,4997.3
Exp/Cntr=0.3,0.1

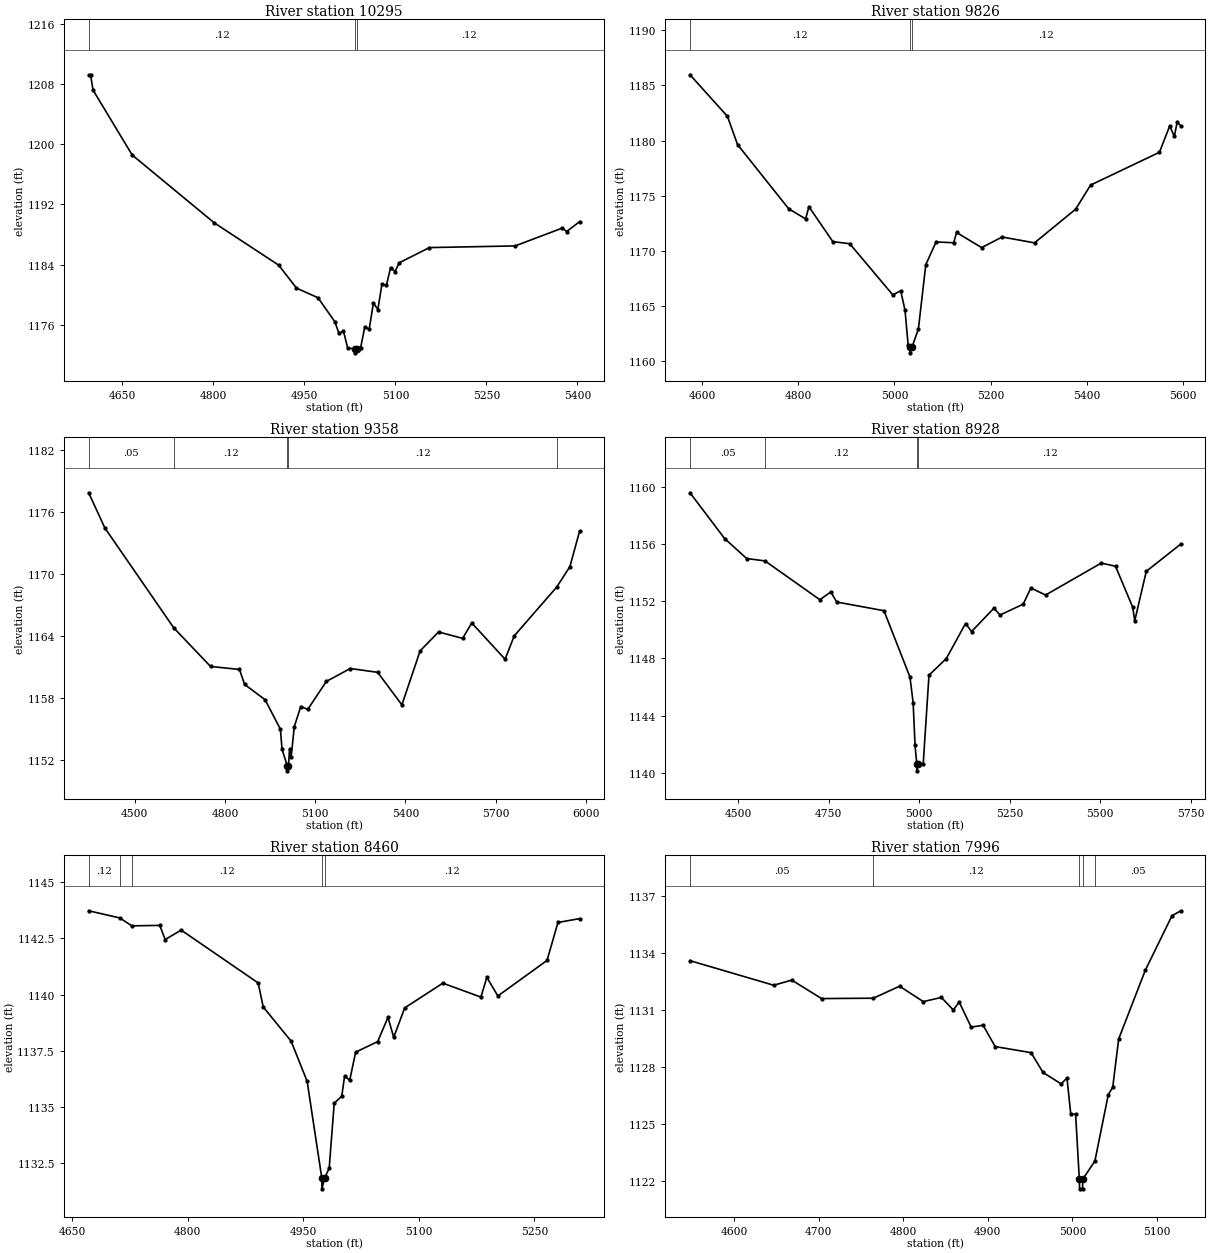
Type RM Length L Ch R = 1,10295,469,469,469
BEGIN DESCRIPTION:
LITTLE LLANO 058 20.0
END DESCRIPTION:
XS GIS Cut Line= 3
      2848905.67     10282953.10      2848581.75     10282709.00
      2848305.67     10283003.13
#Sta/Elev= 30
  4594.4 1209.22  4597.5 1209.22  4601.7 1207.18  4666.2 1198.56  4801.5 1189.55
  4907.7 1183.93  4936.9 1180.89  4972.3 1179.61  5000.0 1176.44  5007.0 1174.86
  5014.3 1175.20  5021.2 1172.95  5033.4 1172.79  5033.6 1172.29  5037.4 1172.79
  5042.7 1172.99  5049.5 1175.75  5056.8 1175.44  5063.7 1178.91  5071.0 1178.04
  5077.8 1181.40  5085.1 1181.25  5092.0 1183.60  5099.3 1183.08  5106.2 1184.25
  5156.0 1186.27  5297.2 1186.49  5375.3 1188.87  5382.1 1188.40  5403.4 1189.70
#Mann=3,-1,0
  4594.4    0.12       0  5033.4    0.07       0  5037.4    0.12       0
Bank Sta=5033.4,5037.4
Exp/Cntr=0.3,0.1

Type RM Length L Ch R = 1,9826,468,468,468
BEGIN DESCRIPTION:
LITTLE LLANO 058 19.0
END DESCRIPTION:
XS GIS Cut Line= 3
      2848855.69     10282553.12      2848564.50     10282243.00
      2848055.66     10282553.13
#Sta/Elev= 30
  4574.6 1185.97  4652.5 1182.20  4673.5 1179.64  4780.0 1173.81  4815.2 1172.89
  4822.0 1174.00  4871.8 1170.83  4907.0 1170.64  4996.5 1166.00  5013.0 1166.37
  5022.0 1164.60  5028.5 1161.43  5032.3 1161.24  5032.6 1160.74  5036.3 1161.24
  5049.8 1162.90  5065.2 1168.74  5086.6 1170.80  5123.3 1170.73  5129.2 1171.66
  5181.4 1170.29  5224.1 1171.25  5291.4 1170.72  5377.1 1173.78  5408.0 1175.96
  5551.4 1178.94  5572.7 1181.33  5582.3 1180.37  5588.1 1181.65  5595.9 1181.34
#Mann=3,-1,0
  4574.6    0.12       0  5032.3    0.07       0  5036.3    0.12       0
Bank Sta=5032.3,5036.3
Exp/Cntr=0.3,0.1

Type RM Length L Ch R = 1,9358,430,430,430
BEGIN DESCRIPTION:
LITTLE LLANO 058 18.0
END DESCRIPTION:
XS GIS Cut Line= 3
      2849005.69     10282403.12      2848724.25     10281813.00
      2847805.69     10282153.11
#Sta/Elev= 30
  4346.2 1177.88  4400.2 1174.47  4629.6 1164.79  4751.7 1161.06  4848.0 1160.77
  4865.1 1159.32  4933.2 1157.84  4984.2 1154.98  4989.7 1153.02  5007.1 1151.45
  5007.4 1150.95  5011.1 1151.45  5014.6 1153.02  5019.9 1152.28  5030.5 1155.23
  5051.8 1157.17  5075.4 1156.91  5137.1 1159.61  5216.7 1160.86  5307.9 1160.49
  5388.4 1157.34  5449.2 1162.57  5510.3 1164.40  5590.5 1163.78  5620.9 1165.27
  5731.8 1161.76  5762.2 1164.02  5903.9 1168.76  5947.5 1170.73  5979.5 1174.14
#Mann=5,-1,0
  4346.2    0.05       0  4629.6    0.12       0  5007.1    0.07       0
  5011.1    0.12       0  5903.9    0.05       0
Bank Sta=5007.1,5011.1
Exp/Cntr=0.3,0.1

Type RM Length L Ch R = 1,8928,468,468,468
BEGIN DESCRIPTION:
LITTLE LLANO 058 17.0
END DESCRIPTION:
XS GIS Cut Line= 3
      2849155.67     10282053.09      2848936.00     10281459.00
      2848255.67     10281703.12
#Sta/Elev= 30
  4366.6 1159.62  4462.3 1156.41  4523.2 1155.01  4573.9 1154.84  4725.4 1152.12
  4755.8 1152.67  4771.7 1151.96  4902.5 1151.35  4974.3 1146.70  4983.1 1144.91
  4988.4 1141.90  4993.1 1140.62  4993.4 1140.12  4997.1 1140.62  5011.0 1140.63
  5026.9 1146.83  5074.7 1147.99  5127.8 1150.45  5144.6 1149.89  5206.1 1151.52
  5223.4 1151.05  5287.2 1151.81  5308.4 1152.94  5349.1 1152.45  5502.9 1154.69
  5542.2 1154.47  5589.8 1151.59  5595.3 1150.64  5627.2 1154.11  5722.8 1156.03
#Mann=4,-1,0
  4366.6    0.05       0  4573.9    0.12       0  4993.1    0.07       0
  4997.1    0.12       0
Bank Sta=4993.1,4997.1
Exp/Cntr=0.3,0.1

Type RM Length L Ch R = 1,8460,464,464,464
BEGIN DESCRIPTION:
LITTLE LLANO 058 16.0
END DESCRIPTION:
XS GIS Cut Line= 3
      2849205.67     10281253.09      2848991.50     10281004.00
      2848755.71     10281203.09
#Sta/Elev= 30
  4671.5 1143.73  4712.1 1143.41  4727.5 1143.06  4763.8 1143.08  4770.8 1142.45
  4791.6 1142.87  4891.5 1140.52  4898.1 1139.45  4934.3 1137.93  4955.1 1136.14
  4974.0 1131.86  4974.2 1131.36  4978.0 1131.86  4983.7 1132.28  4990.2 1135.17
  5000.0 1135.48  5003.7 1136.38  5010.3 1136.19  5018.0 1137.44  5046.6 1137.91
  5060.0 1138.99  5067.4 1138.10  5081.7 1139.41  5131.2 1140.51  5180.6 1139.89
  5188.3 1140.77  5202.6 1139.94  5266.4 1141.52  5280.6 1143.21  5308.6 1143.38
#Mann=5,-1,0
  4671.5    0.12       0  4712.1    0.05       0  4727.5    0.12       0
  4974.0    0.07       0  4978.0    0.12       0
Bank Sta=4974,4978
Exp/Cntr=0.3,0.1

Type RM Length L Ch R = 1,7996,463,463,463
BEGIN DESCRIPTION:
LITTLE LLANO 058 15.0
END DESCRIPTION:
XS GIS Cut Line= 3
      2849305.66     10280853.09      2848977.75     10280542.00
      2848855.69     10280503.11
#Sta/Elev= 30
  4548.0 1133.58  4646.9 1132.29  4668.3 1132.56  4703.5 1131.59  4764.7 1131.61
  4795.7 1132.24  4823.7 1131.43  4845.1 1131.65  4859.2 1130.99  4866.1 1131.41
  4880.3 1130.09  4894.4 1130.19  4908.6 1129.07  4951.1 1128.75  4965.2 1127.71
  4986.6 1127.11  4993.5 1127.42  4998.0 1125.52  5003.7 1125.52  5008.1 1122.10
  5008.4 1121.60  5011.9 1121.60  5012.1 1122.10  5026.5 1123.06  5042.3 1126.54
  5047.6 1126.94  5054.6 1129.47  5086.1 1133.08  5117.6 1135.94  5128.1 1136.20
#Mann=5,-1,0
  4548.0    0.05       0  4764.7    0.12       0  5008.1    0.07       0
  5012.1    0.12       0  5026.5    0.05       0
Bank Sta=5008.1,5012.1
Exp/Cntr=0.3,0.1

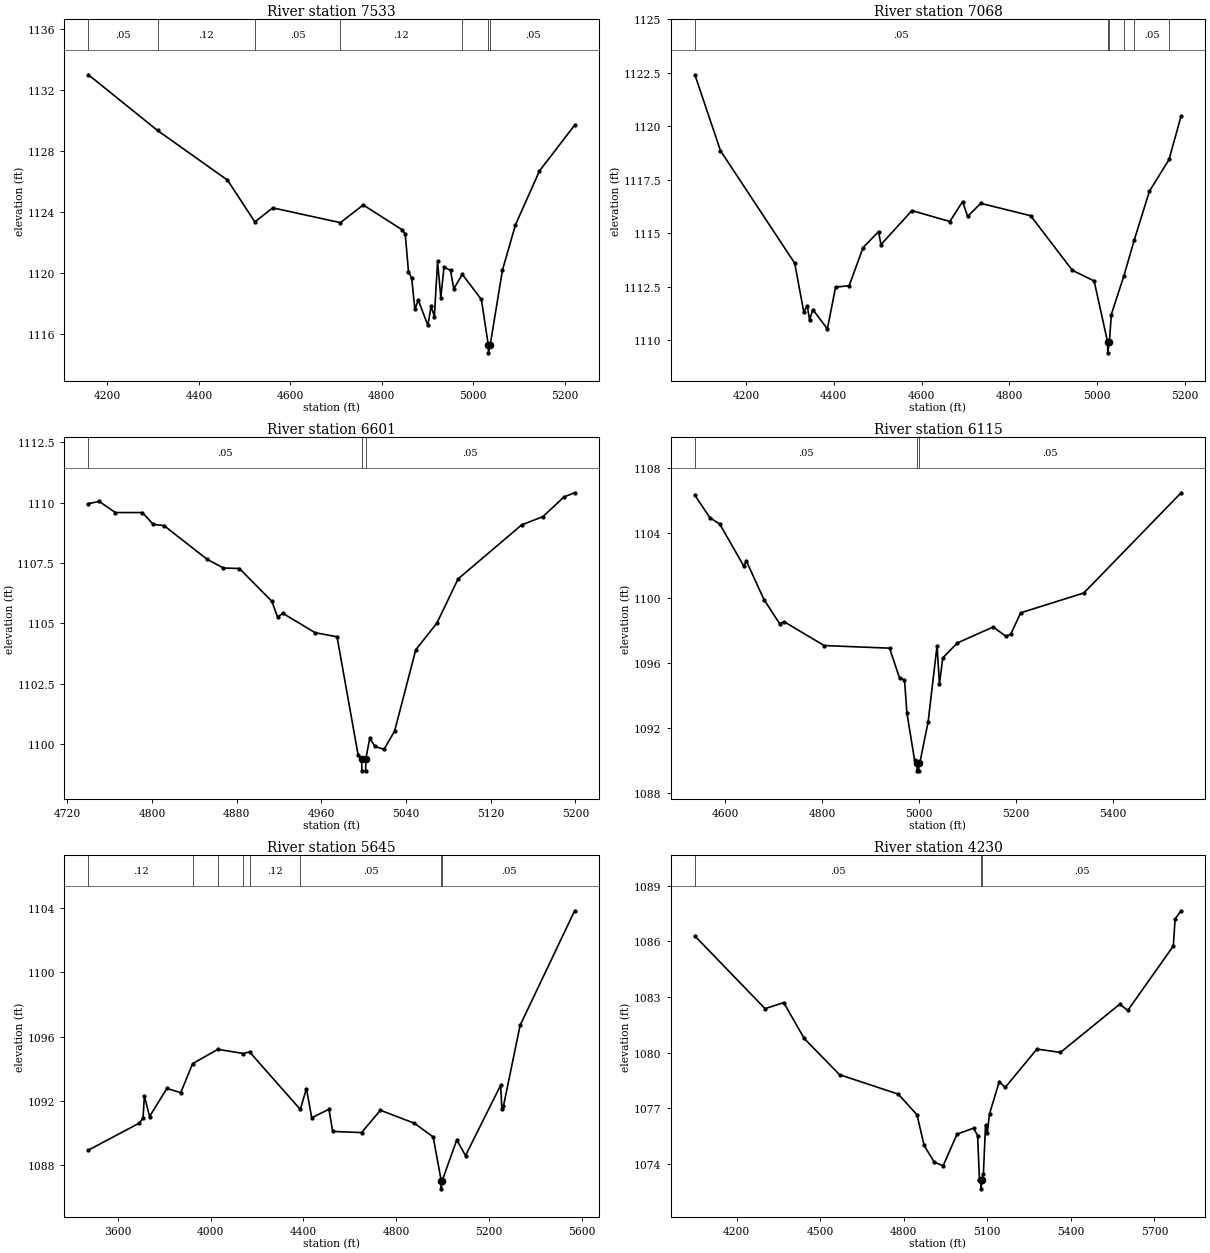
Type RM Length L Ch R = 1,7533,465,465,465
BEGIN DESCRIPTION:
LITTLE LLANO 058 14.0
END DESCRIPTION:
XS GIS Cut Line= 3
      2849655.70     10280703.13      2849057.50     10280111.00
      2848855.72     10280203.09
#Sta/Elev= 30
  4158.3 1133.00  4309.5 1129.35  4462.4 1126.10  4522.4 1123.36  4561.4 1124.28
  4709.4 1123.31  4759.4 1124.47  4844.2 1122.85  4851.3 1122.56  4858.4 1120.10
  4865.4 1119.66  4872.5 1117.62  4879.6 1118.25  4900.8 1116.58  4907.8 1117.82
  4915.0 1117.16  4922.0 1120.77  4929.1 1118.40  4936.1 1120.40  4950.3 1120.18
  4957.4 1118.98  4976.1 1119.92  5017.8 1118.28  5033.0 1115.28  5033.2 1114.78
  5037.0 1115.28  5063.9 1120.20  5092.4 1123.17  5144.9 1126.70  5221.8 1129.70
#Mann=7,-1,0
  4158.3    0.05       0  4309.5    0.12       0  4522.4    0.05       0
  4709.4    0.12       0  4976.1    0.05       0  5033.0    0.05       0
  5037.0    0.05       0
Bank Sta=5033,5037
Exp/Cntr=0.3,0.1

Type RM Length L Ch R = 1,7068,467,467,467
BEGIN DESCRIPTION:
LITTLE LLANO 058 13.0
END DESCRIPTION:
XS GIS Cut Line= 3
      2849805.69     10279953.11      2848918.75     10279723.00
      2848855.70     10279903.08
#Sta/Elev= 30
  4083.7 1122.40  4142.0 1118.85  4311.0 1113.59  4331.6 1111.32  4339.7 1111.60
  4344.8 1110.94  4352.3 1111.42  4385.4 1110.52  4404.0 1112.47  4435.0 1112.54
  4466.6 1114.32  4502.0 1115.07  4507.3 1114.46  4577.9 1116.05  4664.2 1115.54
  4693.2 1116.47  4704.8 1115.78  4734.6 1116.39  4848.2 1115.81  4943.1 1113.26
  4992.8 1112.76  5023.5 1109.90  5023.8 1109.40  5027.5 1109.90  5031.9 1111.19
  5060.7 1113.01  5084.0 1114.67  5118.6 1116.95  5163.3 1118.44  5190.8 1120.47
#Mann=6,-1,0
  4083.7    0.05       0  5023.5    0.03       0  5027.5    0.05       0
  5060.7    0.12       0  5084.0    0.05       0  5163.3    0.12       0
Bank Sta=5023.5,5027.5
Exp/Cntr=0.3,0.1

Type RM Length L Ch R = 1,6601,486,486,486
BEGIN DESCRIPTION:
LITTLE LLANO 058 12.0
END DESCRIPTION:
XS GIS Cut Line= 3
      2848805.68     10279453.11      2848550.50     10279504.00
      2848555.68     10279703.13
#Sta/Elev= 30
  4739.8 1109.96  4750.0 1110.05  4765.3 1109.59  4790.8 1109.59  4801.0 1109.10
  4811.2 1109.05  4852.0 1107.65  4867.4 1107.29  4882.5 1107.27  4913.1 1105.91
  4918.5 1105.26  4923.6 1105.41  4953.9 1104.61  4974.7 1104.44  4994.7 1099.52
  4997.9 1099.38  4998.2 1098.88  5001.7 1098.88  5001.9 1099.38  5005.6 1100.23
  5010.6 1099.89  5019.1 1099.77  5029.1 1100.53  5049.1 1103.90  5069.1 1105.01
  5089.1 1106.84  5149.2 1109.08  5169.2 1109.42  5189.2 1110.24  5199.2 1110.41
#Mann=3,-1,0
  4739.8    0.05       0  4997.9    0.03       0  5001.9    0.05       0
Bank Sta=4997.9,5001.9
Exp/Cntr=0.3,0.1

Type RM Length L Ch R = 1,6115,470,470,470
BEGIN DESCRIPTION:
LITTLE LLANO 058 11.0
END DESCRIPTION:
XS GIS Cut Line= 3
      2848655.70     10279053.11      2848207.00     10279164.00
      2848255.68     10279703.11
#Sta/Elev= 30
  4537.8 1106.32  4568.7 1104.94  4589.3 1104.54  4638.8 1101.96  4644.0 1102.28
  4680.3 1099.91  4712.9 1098.42  4721.7 1098.55  4804.6 1097.08  4939.6 1096.92
  4960.2 1095.08  4970.4 1094.97  4975.5 1092.92  4991.1 1090.06  4996.1 1089.88
  4996.4 1089.38  4999.9 1089.38  5000.1 1089.88  5002.1 1089.88  5019.2 1092.39
  5037.6 1097.07  5042.6 1094.71  5049.3 1096.32  5079.4 1097.24  5153.4 1098.22
  5179.8 1097.65  5189.9 1097.78  5210.0 1099.09  5340.5 1100.31  5541.3 1106.47
#Mann=3,-1,0
  4537.8    0.05       0  4996.1    0.03       0  5000.1    0.05       0
Bank Sta=4996.1,5000.1
Exp/Cntr=0.3,0.1

Type RM Length L Ch R = 1,5645,1415,1415,1415
BEGIN DESCRIPTION:
LITTLE LLANO 058 10.0
END DESCRIPTION:
XS GIS Cut Line= 3
      2849105.72     10278253.09      2847772.75     10278997.00
      2847655.68     10279553.11
#Sta/Elev= 30
  3473.5 1088.95  3692.9 1090.63  3708.9 1090.96  3714.6 1092.32  3736.9 1091.04
  3811.7 1092.79  3871.2 1092.52  3922.3 1094.33  4031.4 1095.22  4141.0 1094.96
  4167.7 1095.06  4386.5 1091.48  4412.8 1092.78  4435.5 1090.96  4509.9 1091.49
  4525.9 1090.11  4650.4 1090.04  4731.5 1091.43  4877.8 1090.62  4958.9 1089.77
  4993.5 1087.04  4993.7 1086.54  4997.5 1087.04  5060.5 1089.58  5098.2 1088.61
  5249.6 1092.99  5254.7 1091.51  5261.7 1091.69  5333.3 1096.71  5568.3 1103.84
#Mann=8,-1,0
  3473.5    0.12       0  3922.3    0.05       0  4031.4    0.12       0
  4141.0    0.05       0  4167.7    0.12       0  4386.5    0.05       0
  4993.5    0.03       0  4997.5    0.05       0
Bank Sta=4993.5,4997.5
Exp/Cntr=0.3,0.1

Type RM Length L Ch R = 1,4230,470,470,470
BEGIN DESCRIPTION:
LITTLE LLANO 058 9.0
END DESCRIPTION:
XS GIS Cut Line= 3
      2847605.66     10278703.10      2846710.25     10278386.00
      2846105.65     10278903.14
#Sta/Elev= 30
  4050.1 1086.28  4302.0 1082.37  4369.1 1082.69  4442.6 1080.76  4569.4 1078.81
  4780.4 1077.76  4847.5 1076.65  4873.0 1075.00  4909.4 1074.10  4941.2 1073.90
  4991.3 1075.61  5050.7 1075.93  5065.0 1075.53  5071.8 1073.16  5077.3 1073.16
  5077.5 1072.66  5081.3 1073.16  5085.9 1073.48  5093.5 1076.09  5100.1 1075.69
  5107.8 1076.70  5142.9 1078.44  5163.9 1078.12  5278.0 1080.19  5362.5 1080.01
  5575.5 1082.61  5604.0 1082.27  5767.6 1085.74  5774.1 1087.20  5795.6 1087.64
#Mann=3,-1,0
  4050.1    0.05       0  5077.3    0.03       0  5081.3    0.05       0
Bank Sta=5077.3,5081.3
Exp/Cntr=0.3,0.1

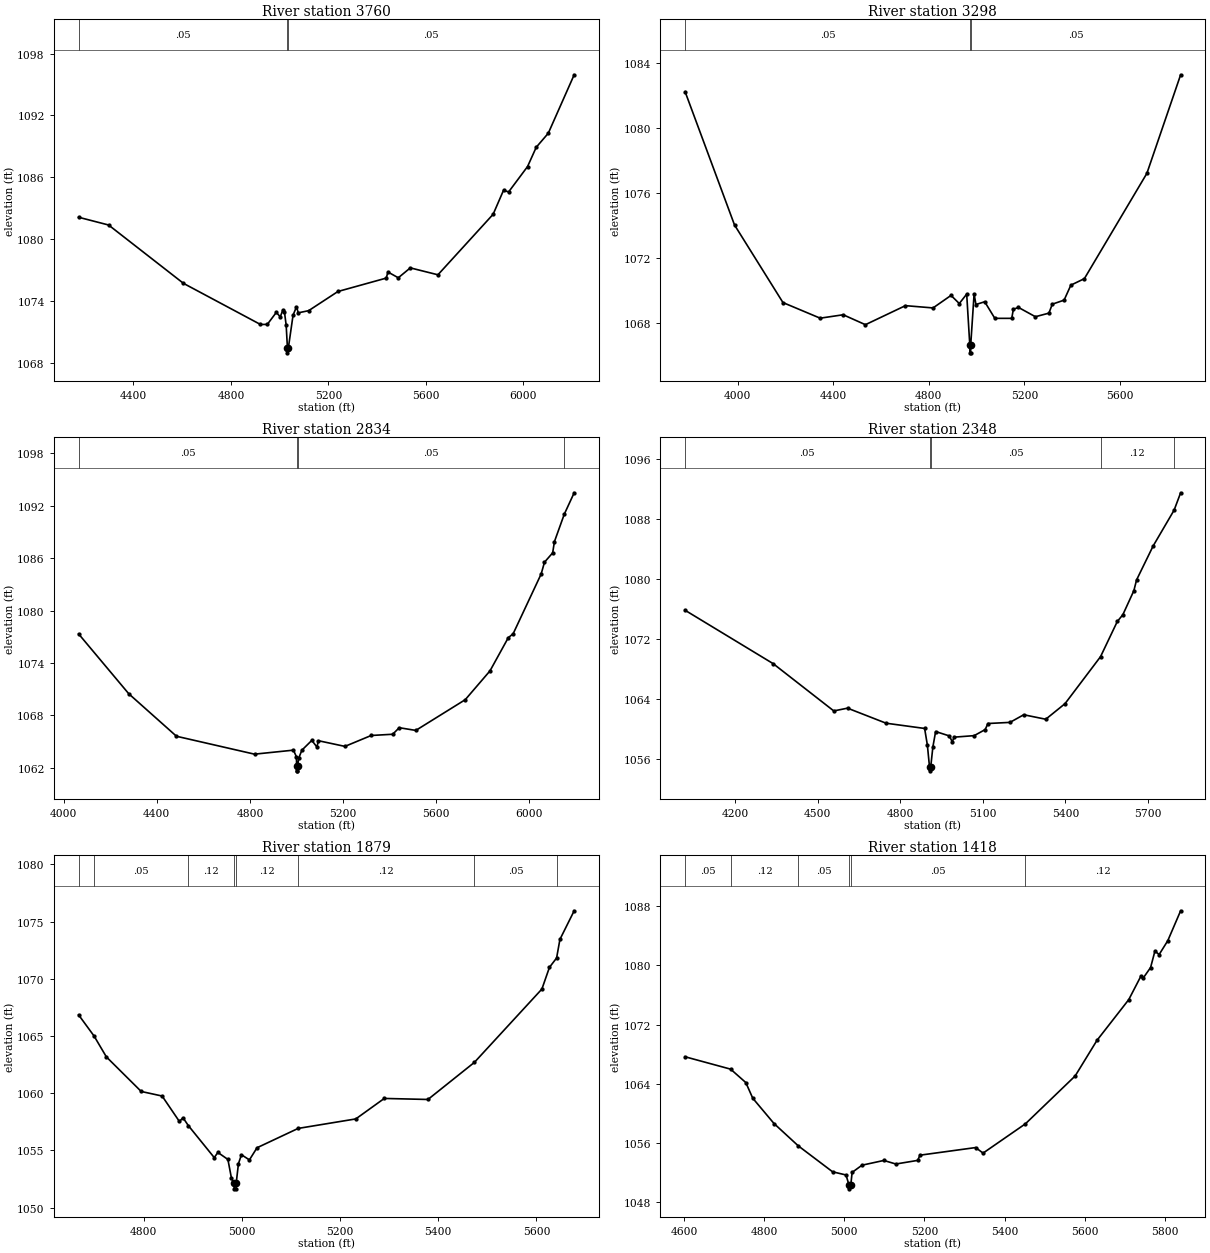
Type RM Length L Ch R = 1,3760,462,462,462
BEGIN DESCRIPTION:
LITTLE LLANO 058 8.0
END DESCRIPTION:
XS GIS Cut Line= 3
      2847405.65     10278403.09      2846734.50     10277924.00
      2845855.68     10278753.11
#Sta/Elev= 30
  4175.4 1082.12  4298.2 1081.37  4605.4 1075.71  4921.4 1071.72  4949.4 1071.73
  4986.3 1072.89  5002.6 1072.46  5012.5 1073.09  5019.8 1072.92  5026.7 1071.67
  5031.9 1069.47  5032.2 1068.97  5035.9 1069.47  5055.0 1072.62  5069.1 1073.44
  5076.4 1072.85  5118.9 1073.06  5239.1 1074.92  5437.3 1076.22  5444.2 1076.81
  5486.7 1076.25  5536.0 1077.21  5649.3 1076.54  5875.8 1082.41  5918.3 1084.73
  5939.4 1084.58  6017.0 1087.04  6052.6 1088.91  6102.0 1090.27  6208.2 1095.94
#Mann=3,-1,0
  4175.4    0.05       0  5031.9    0.03       0  5035.9    0.05       0
Bank Sta=5031.9,5035.9
Exp/Cntr=0.3,0.1

Type RM Length L Ch R = 1,3298,464,464,464
BEGIN DESCRIPTION:
LITTLE LLANO 058 7.0
END DESCRIPTION:
XS GIS Cut Line= 3
      2847605.72     10277303.10      2846425.75     10277615.00
      2845805.69     10278203.11
#Sta/Elev= 30
  3779.5 1082.23  3986.4 1074.04  4189.3 1069.27  4345.1 1068.31  4441.5 1068.52
  4534.6 1067.91  4702.2 1069.08  4817.8 1068.94  4893.1 1069.71  4927.7 1069.21
  4958.7 1069.79  4971.6 1066.68  4971.9 1066.18  4975.4 1066.18  4975.6 1066.68
  4989.7 1069.80  4997.4 1069.15  5034.1 1069.32  5076.5 1068.30  5147.3 1068.30
  5154.2 1068.86  5175.6 1068.97  5246.4 1068.40  5303.0 1068.62  5317.1 1069.17
  5366.6 1069.42  5394.9 1070.34  5451.5 1070.74  5713.2 1077.21  5854.6 1083.27
#Mann=3,-1,0
  3779.5    0.05       0  4971.6    0.03       0  4975.6    0.05       0
Bank Sta=4971.6,4975.6
Exp/Cntr=0.3,0.1

Type RM Length L Ch R = 1,2834,486,486,486
BEGIN DESCRIPTION:
LITTLE LLANO 058 6.0
END DESCRIPTION:
XS GIS Cut Line= 3
      2847355.70     10276953.11      2846443.00     10277157.00
      2845555.69     10277953.11
#Sta/Elev= 30
  4064.8 1077.33  4280.0 1070.48  4484.9 1065.61  4819.8 1063.56  4987.0 1064.02
  5000.0 1063.24  5000.4 1062.15  5000.6 1061.65  5004.1 1061.65  5004.4 1062.15
  5009.8 1063.12  5023.3 1064.02  5065.9 1065.14  5087.6 1064.38  5094.3 1065.10
  5208.0 1064.45  5320.8 1065.70  5412.9 1065.84  5441.2 1066.59  5512.2 1066.28
  5724.5 1069.80  5830.7 1073.10  5909.2 1076.90  5930.1 1077.35  6050.4 1084.20
  6064.7 1085.55  6099.8 1086.62  6107.3 1087.90  6149.7 1091.05  6192.1 1093.50
#Mann=4,-1,0
  4064.8    0.05       0  5000.4    0.03       0  5004.4    0.05       0
  6149.7    0.12       0
Bank Sta=5000.4,5004.4
Exp/Cntr=0.3,0.1

Type RM Length L Ch R = 1,2348,469,469,469
BEGIN DESCRIPTION:
LITTLE LLANO 058 5.0
END DESCRIPTION:
XS GIS Cut Line= 3
      2847205.72     10276753.11      2846224.25     10276761.00
      2845405.69     10276753.11
#Sta/Elev= 30
  4018.5 1075.80  4338.5 1068.67  4558.6 1062.36  4608.6 1062.73  4748.6 1060.72
  4888.6 1060.02  4898.6 1057.80  4906.4 1054.86  4906.7 1054.36  4910.7 1054.86
  4918.6 1057.56  4928.6 1059.61  4978.6 1059.02  4988.6 1058.26  4996.8 1058.86
  5068.6 1059.06  5108.6 1059.87  5118.6 1060.68  5198.6 1060.83  5248.6 1061.85
  5328.6 1061.25  5398.6 1063.33  5527.7 1069.61  5588.6 1074.31  5608.6 1075.20
  5648.6 1078.41  5658.6 1079.86  5718.6 1084.38  5795.0 1089.18  5818.6 1091.49
#Mann=5,-1,0
  4018.5    0.05       0  4906.4    0.05       0  4910.7    0.05       0
  5527.7    0.12       0  5795.0    0.05       0
Bank Sta=4906.4,4910.7
Exp/Cntr=0.3,0.1

Type RM Length L Ch R = 1,1879,461,461,461
BEGIN DESCRIPTION:
LITTLE LLANO 058 4.0
END DESCRIPTION:
XS GIS Cut Line= 3
      2846405.70     10276053.09      2846182.50     10276299.00
      2845605.72     10276653.09
#Sta/Elev= 30
  4667.9 1066.84  4699.4 1064.99  4724.4 1063.17  4795.3 1060.15  4837.9 1059.75
  4873.0 1057.53  4880.5 1057.85  4891.2 1057.17  4944.0 1054.37  4951.4 1054.82
  4971.8 1054.21  4979.1 1052.56  4984.4 1052.14  4984.7 1051.64  4988.4 1051.64
  4988.7 1052.14  4993.3 1053.84  4999.4 1054.62  5015.6 1054.17  5031.1 1055.23
  5114.8 1056.92  5232.2 1057.75  5290.2 1059.54  5379.1 1059.45  5473.6 1062.69
  5611.1 1069.10  5626.5 1071.00  5641.0 1071.81  5647.8 1073.44  5676.8 1075.94
#Mann=8,-1,0
  4667.9    0.12       0  4699.4    0.05       0  4891.2    0.12       0
  4984.4    0.05       0  4988.7    0.12       0  5114.8    0.12       0
  5473.6    0.05       0  5641.0    0.12       0
Bank Sta=4984.4,4988.7
Exp/Cntr=0.3,0.1

Type RM Length L Ch R = 1,1418,465,465,465
BEGIN DESCRIPTION:
LITTLE LLANO 058 3.0
END DESCRIPTION:
XS GIS Cut Line= 3
      2846455.67     10276003.11      2846088.75     10275851.00
      2845305.71     10276153.10
#Sta/Elev= 30
  4602.8 1067.65  4716.4 1065.98  4754.3 1064.17  4771.6 1062.06  4824.7 1058.64
  4885.2 1055.63  4970.8 1052.13  5004.3 1051.70  5011.9 1050.33  5012.2 1049.83
  5016.2 1050.33  5019.6 1052.05  5044.2 1053.02  5098.7 1053.66  5128.7 1053.18
  5183.3 1053.67  5188.7 1054.37  5327.8 1055.40  5346.3 1054.65  5451.9 1058.60
  5576.1 1065.06  5630.6 1069.87  5709.8 1075.36  5739.8 1078.49  5745.2 1078.22
  5764.3 1079.69  5775.1 1081.90  5785.7 1081.45  5807.2 1083.31  5839.3 1087.35
#Mann=6,-1,0
  4602.8    0.05       0  4716.4    0.12       0  4885.2    0.05       0
  5011.9    0.05       0  5016.2    0.05       0  5451.9    0.12       0
Bank Sta=5011.9,5016.2
Exp/Cntr=0.3,0.1

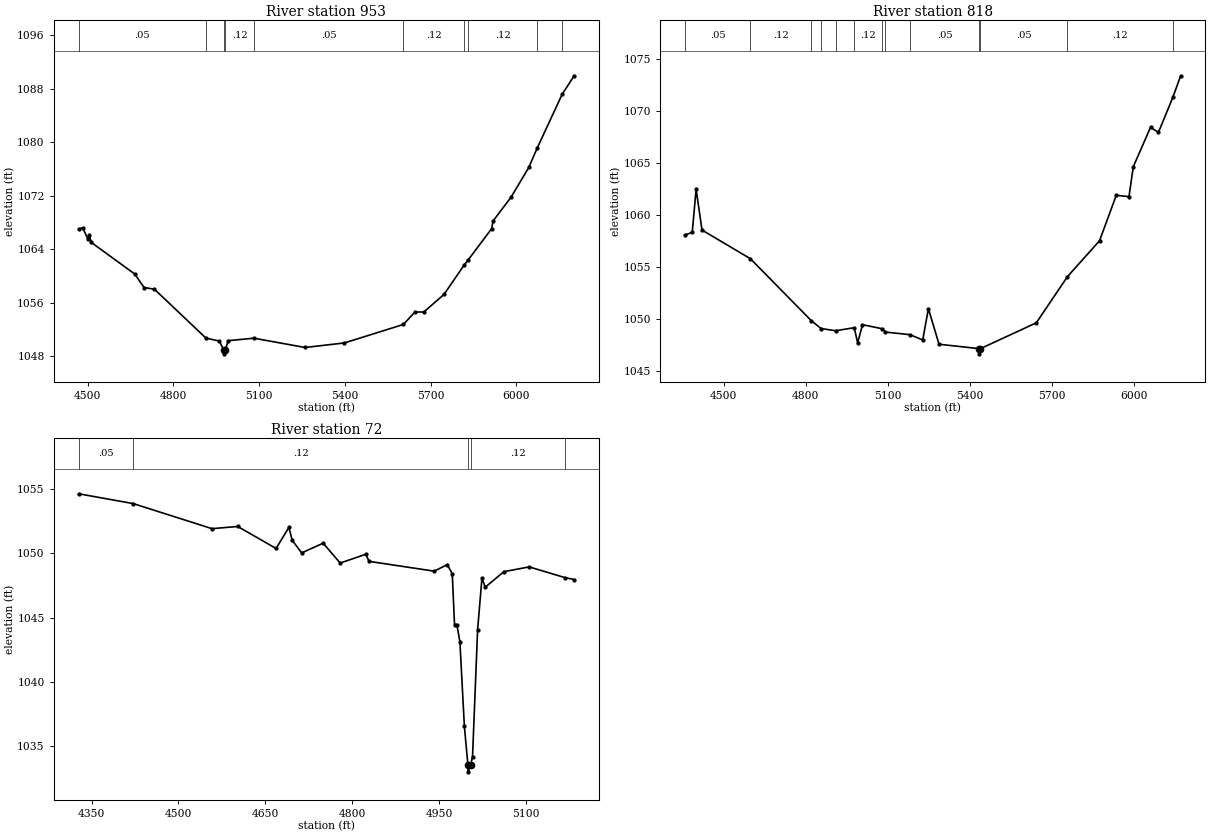
Type RM Length L Ch R = 1,953,135,135,135
BEGIN DESCRIPTION:
LITTLE LLANO 058 2.0
END DESCRIPTION:
XS GIS Cut Line= 3
      2846505.68     10275953.09      2846293.75     10275466.00
      2845105.69     10275653.11
#Sta/Elev= 30
  4468.8 1066.98  4483.2 1067.17  4501.2 1065.50  4506.7 1066.14  4512.4 1065.02
  4665.1 1060.27  4697.8 1058.25  4734.0 1058.00  4914.3 1050.68  4961.3 1050.24
  4977.1 1048.83  4977.4 1048.33  4981.5 1048.83  4992.2 1050.30  5082.0 1050.67
  5261.2 1049.28  5398.6 1049.96  5604.9 1052.72  5645.9 1054.60  5676.3 1054.58
  5747.2 1057.22  5818.9 1061.68  5832.3 1062.41  5913.8 1067.05  5919.3 1068.23
  5981.4 1071.74  6043.9 1076.21  6073.9 1079.17  6160.9 1087.18  6202.7 1089.93
#Mann=10,-1,0
  4468.8    0.05       0  4914.3    0.12       0  4977.1    0.07       0
  4981.5    0.12       0  5082.0    0.05       0  5604.9    0.12       0
  5818.9    0.05       0  5832.3    0.12       0  6073.9    0.05       0
  6160.9    0.12       0
Bank Sta=4977.1,4981.5
Exp/Cntr=0.3,0.1

Type RM Length L Ch R = 1,818,746,746,746
BEGIN DESCRIPTION:
Mapping XS d5794dca
END DESCRIPTION:
XS GIS Cut Line= 4
      2846856.07     10275799.77      2846495.72     10275406.67
      2845971.62     10275242.89      2845269.03     10275438.95
#Sta/Elev= 30
  4359.0 1058.10  4385.1 1058.33  4399.3 1062.49  4420.8 1058.56  4597.6 1055.81
  4821.0 1049.84  4856.2 1049.10  4909.3 1048.89  4977.4 1049.18  4989.9 1047.72
  5007.6 1049.47  5079.5 1049.08  5091.7 1048.76  5181.6 1048.51  5227.8 1048.00
  5248.5 1051.00  5287.5 1047.59  5434.4 1047.17  5434.7 1046.67  5438.8 1047.17
  5643.2 1049.65  5757.0 1054.09  5874.2 1057.53  5935.5 1061.90  5981.9 1061.77
  5997.8 1064.65  6060.7 1068.43  6089.6 1067.94  6142.8 1071.34  6170.8 1073.38
#Mann=13,-1,0
  4359.0    0.05       0  4597.6    0.12       0  4821.0    0.05       0
  4856.2    0.12       0  4909.3    0.05       0  4977.4    0.12       0
  5079.5    0.05       0  5091.7    0.12       0  5181.6    0.05       0
  5434.4    0.07       0  5438.8    0.05       0  5757.0    0.12       0
  6142.8    0.05       0
Bank Sta=5434.4,5438.8
Exp/Cntr=0.3,0.1

Type RM Length L Ch R = 1,72,0,0,0
BEGIN DESCRIPTION:
LITTLE LLANO 058 1.0
END DESCRIPTION:
XS GIS Cut Line= 3
      2846959.30     10275287.59      2846659.94     10274711.18
      2846479.34     10274612.73
#Sta/Elev= 30
  4327.7 1054.62  4421.7 1053.86  4557.9 1051.91  4602.2 1052.08  4668.5 1050.37
  4690.6 1052.01  4696.3 1051.00  4712.7 1050.03  4749.7 1050.78  4779.1 1049.24
  4823.3 1049.92  4829.0 1049.37  4941.2 1048.61  4963.8 1049.11  4972.5 1048.42
  4976.4 1044.46  4980.4 1044.46  4985.7 1043.12  4993.4 1036.56  4999.6 1033.52
  4999.9 1033.02  5004.1 1033.52  5007.5 1034.21  5016.2 1044.02  5023.7 1048.06
  5029.4 1047.36  5061.6 1048.57  5105.3 1048.94  5167.5 1048.10  5182.9 1047.96
#Mann=5,-1,0
  4327.7    0.05       0  4421.7    0.12       0  4999.6    0.07       0
  5004.1    0.12       0  5167.5    0.05       0
Bank Sta=4999.6,5004.1
Exp/Cntr=0.3,0.1

Chan Stop Cuts=-1