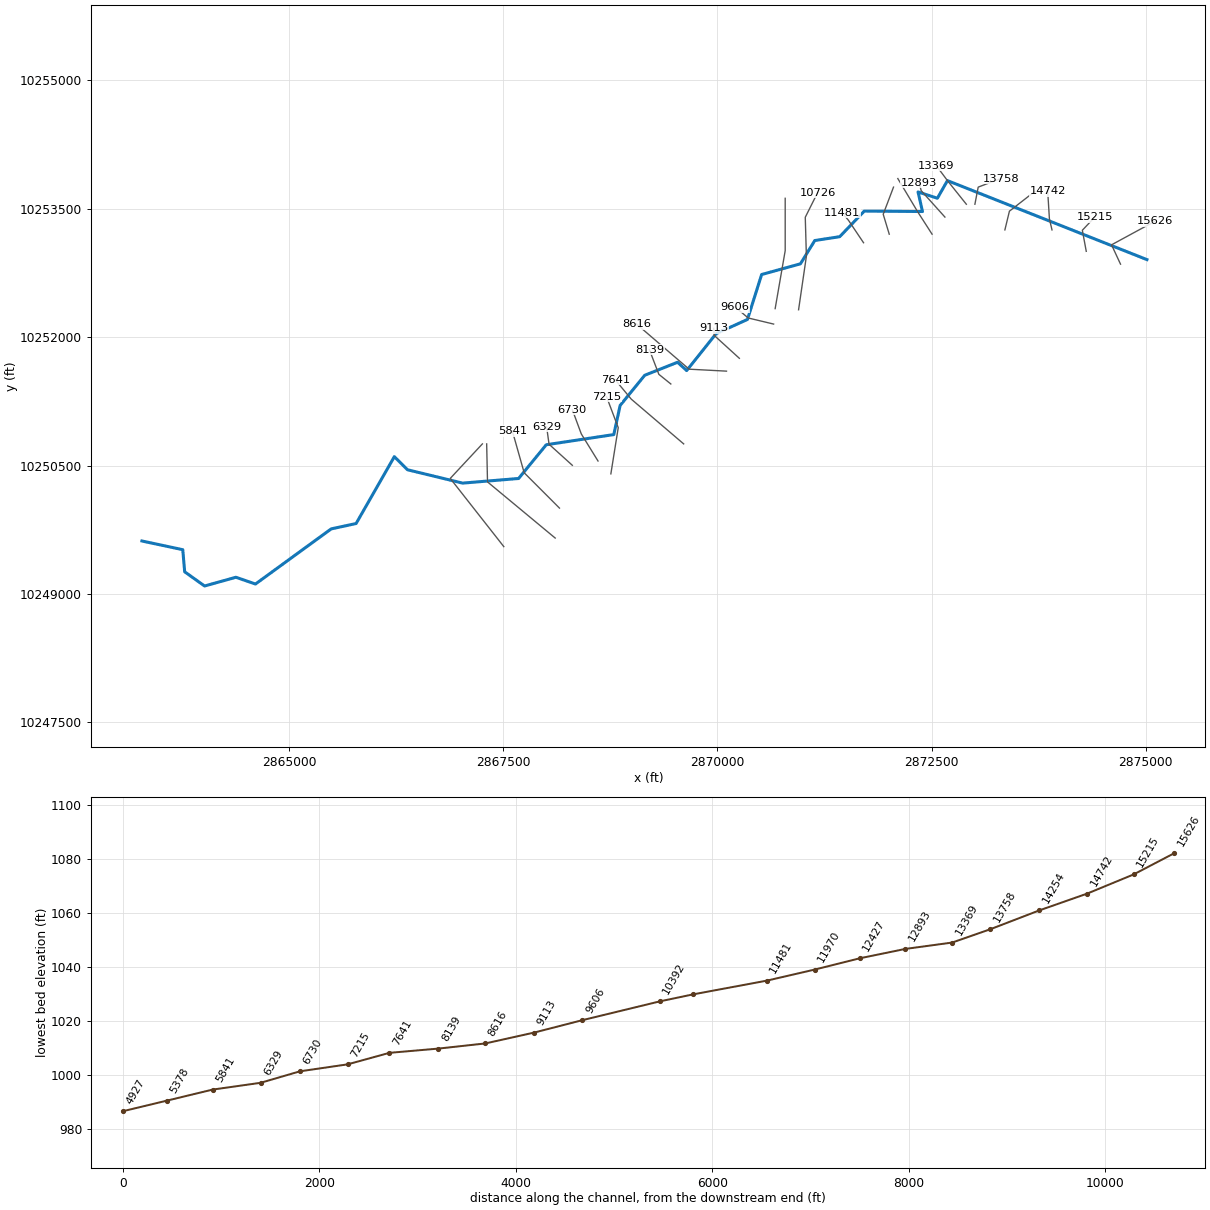
--- LITTLE LLANO 060.prj (project) ---

Proj Title=LITTLE LLANO 060 Base Level Engineering
Current Plan=p01
Default Exp/Contr=0.3,0.1
English Units
Geom File=g01
Flow File=f01
Plan File=p01
BEGIN DESCRIPTION:
LITTLE LLANO 060
END DESCRIPTION:

--- LITTLE LLANO 060.p01 (plan) ---

Plan Title=Multiple Run
Short Identifier=Multiple
Geom File=g01
Flow File=f01
Subcritical Flow
K Sum by GR= 0
Std Step Tol= 0.01
Critical Tol= 0.01
Num of Std Step Trials= 20
Max Error Tol= 0.3
Flow Tol Ratio= 0.001
Split Flow NTrial= 30
Split Flow Tol= 0.02
Split Flow Ratio= 0.02
Log Output Level= 0
Friction Slope Method= 1
Unsteady Friction Slope Method= 2
Unsteady Bridges Friction Slope Method= 1
Parabolic Critical Depth
Global Vel Dist=  1 , 1 , 1
Global Log Level= 0
CheckData=True
Encroach Param= -1, 0, 0, 0
BEGIN DESCRIPTION:
Multiple Run
END DESCRIPTION:

--- LITTLE LLANO 060.f01 (steady flow) ---

Flow Title=Multiple
Number of Profiles=7
Profile Names=10-year,25-year,50-year,1pct_min,100-year,1pct_plu,500-year
River Rch & RM= LITTLE LLANO 060,Reach-1,15626
      66     127     198     103     311     940     821
River Rch & RM= LITTLE LLANO 060,Reach-1,5841
      93     190     304     161     487    1469    1325
Boundary for River Rch & Prof#=LITTLE LLANO 060,Reach-1,1
Up Type=0
Dn Type=3
Dn Slope=0.005
Boundary for River Rch & Prof#=LITTLE LLANO 060,Reach-1,2
Up Type=0
Dn Type=3
Dn Slope=0.005
Boundary for River Rch & Prof#=LITTLE LLANO 060,Reach-1,3
Up Type=0
Dn Type=3
Dn Slope=0.005
Boundary for River Rch & Prof#=LITTLE LLANO 060,Reach-1,4
Up Type=0
Dn Type=3
Dn Slope=0.005
Boundary for River Rch & Prof#=LITTLE LLANO 060,Reach-1,5
Up Type=0
Dn Type=3
Dn Slope=0.005
Boundary for River Rch & Prof#=LITTLE LLANO 060,Reach-1,6
Up Type=0
Dn Type=3
Dn Slope=0.005
Boundary for River Rch & Prof#=LITTLE LLANO 060,Reach-1,7
Up Type=0
Dn Type=3
Dn Slope=0.005

--- LITTLE LLANO 060.g01 (geometry) ---

Geom Title=Existing Conditions

River Reach=LITTLE LLANO 060,Reach-1
Reach XY= 30
      2875014.25     10252906.00      2872685.25     10253829.00
      2872567.50     10253623.00      2872342.00     10253697.00
      2872393.50     10253468.00      2871714.25     10253473.00
      2871427.50     10253174.00      2871136.25     10253129.00
      2870969.00     10252857.00      2870516.00     10252732.00
      2870350.25     10252207.00      2869984.50     10252041.00
      2869640.75     10251610.00      2869534.50     10251707.00
      2869151.25     10251555.00      2868863.75     10251202.00
      2868790.00     10250862.00      2868001.25     10250743.00
      2867678.50     10250349.00      2867024.25     10250295.00
      2866381.50     10250451.00      2866227.75     10250604.00
      2865781.50     10249823.00      2865490.50     10249760.00
      2864606.50     10249116.00      2864378.25     10249195.00
      2864012.25     10249093.00      2863780.00     10249259.00
      2863757.75     10249517.00      2863281.00     10249619.00

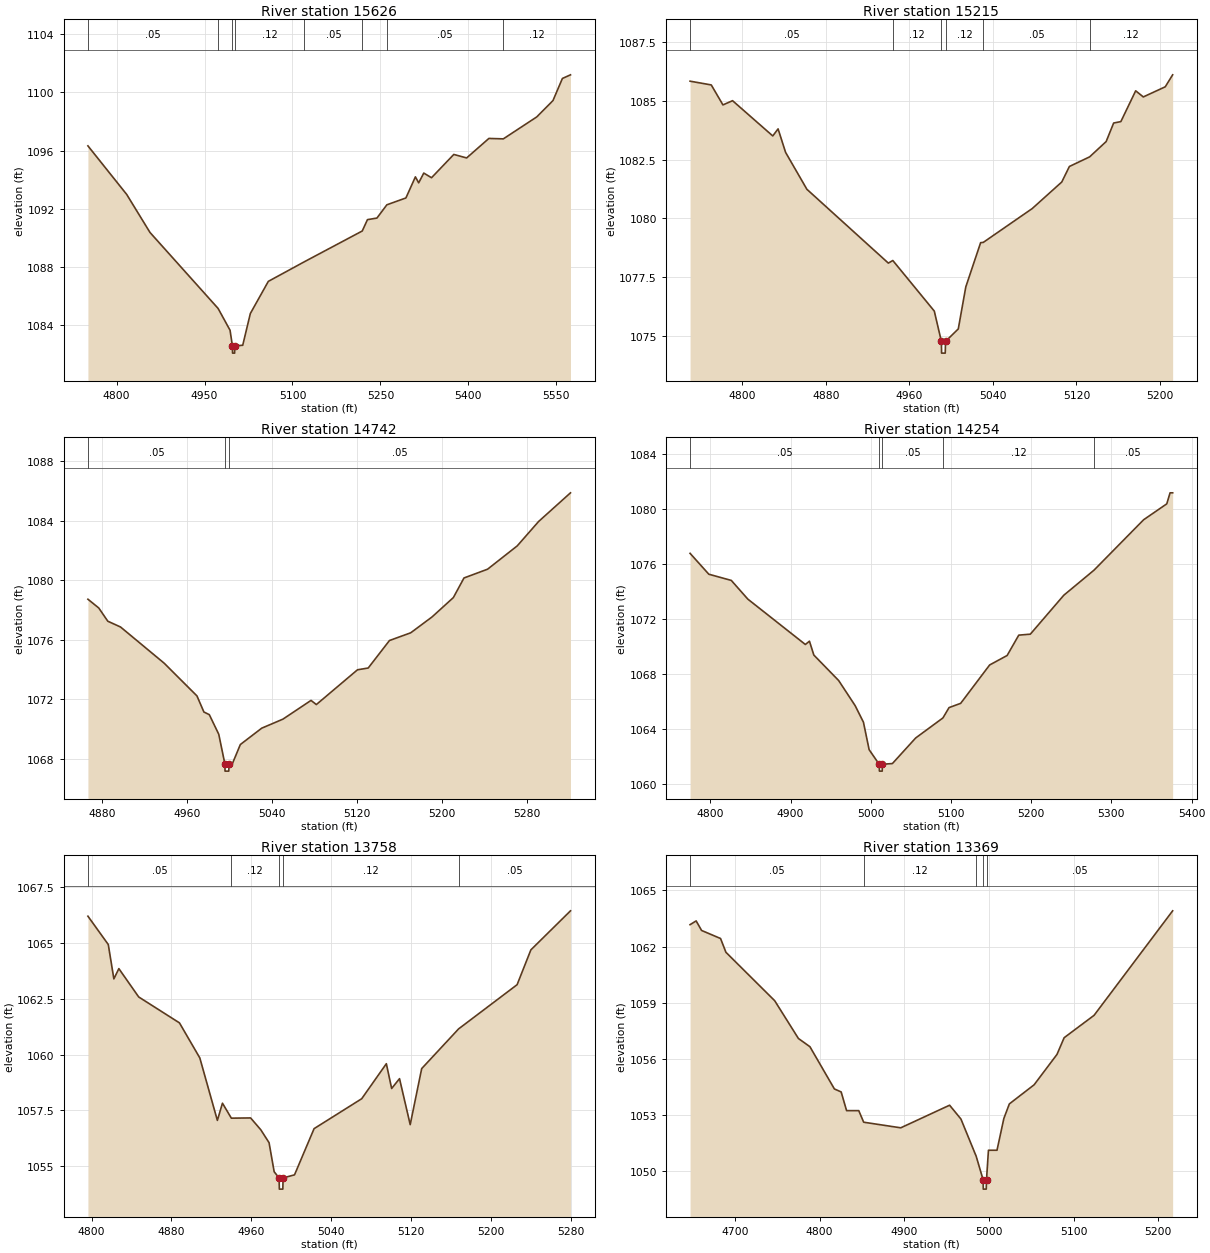
Type RM Length L Ch R = 1,15626,411,411,411
BEGIN DESCRIPTION:
LITTLE LLANO 060 24.0
END DESCRIPTION:
XS GIS Cut Line= 3
      2874705.70     10252853.08      2874601.00     10253079.00
      2875105.67     10253353.10
#Sta/Elev= 30
  4751.0 1096.33  4817.2 1092.99  4856.9 1090.38  4973.1 1085.16  4993.5 1083.66
  4997.5 1082.59  4997.8 1082.09  5001.3 1082.09  5001.5 1082.59  5015.1 1082.63
  5028.1 1084.81  5058.8 1087.02  5120.4 1088.37  5219.0 1090.48  5227.9 1091.26
  5244.1 1091.37  5261.0 1092.28  5293.5 1092.75  5309.7 1094.20  5315.3 1093.79
  5324.0 1094.46  5337.2 1094.14  5375.2 1095.74  5397.1 1095.50  5435.1 1096.84
  5459.7 1096.81  5516.8 1098.32  5544.4 1099.44  5560.5 1100.96  5574.3 1101.21
#Mann=8,-1,0
  4751.0    0.05       0  4973.1    0.12       0  4997.5    0.07       0
  5001.5    0.12       0  5120.4    0.05       0  5219.0    0.12       0
  5261.0    0.05       0  5459.7    0.12       0
Bank Sta=4997.5,5001.5
Exp/Cntr=0.3,0.1

Type RM Length L Ch R = 1,15215,473,473,473
BEGIN DESCRIPTION:
LITTLE LLANO 060 23.0
END DESCRIPTION:
XS GIS Cut Line= 3
      2874305.68     10253003.11      2874260.00     10253249.00
      2874405.70     10253403.13
#Sta/Elev= 30
  4749.9 1085.84  4770.2 1085.68  4781.4 1084.83  4790.6 1085.01  4829.1 1083.51
  4834.2 1083.81  4841.4 1082.81  4861.8 1081.24  4939.8 1078.10  4944.1 1078.21
  4983.8 1076.06  4990.6 1074.77  4990.8 1074.27  4994.3 1074.27  4994.6 1074.77
  5006.8 1075.30  5014.0 1077.09  5028.2 1078.97  5030.7 1078.98  5077.6 1080.42
  5105.9 1081.55  5113.2 1082.21  5132.6 1082.62  5148.4 1083.27  5155.6 1084.06
  5162.5 1084.12  5176.7 1085.43  5184.0 1085.17  5205.0 1085.60  5212.1 1086.11
#Mann=6,-1,0
  4749.9    0.05       0  4944.1    0.12       0  4990.6    0.07       0
  4994.6    0.12       0  5030.7    0.05       0  5132.6    0.12       0
Bank Sta=4990.6,4994.6
Exp/Cntr=0.3,0.1

Type RM Length L Ch R = 1,14742,488,488,488
BEGIN DESCRIPTION:
LITTLE LLANO 060 22.0
END DESCRIPTION:
XS GIS Cut Line= 3
      2873905.67     10253253.16      2873875.50     10253383.00
      2873855.69     10253703.09
#Sta/Elev= 30
  4866.7 1078.73  4876.9 1078.14  4885.4 1077.25  4897.4 1076.86  4938.5 1074.42
  4969.3 1072.22  4975.8 1071.14  4980.9 1070.96  4989.8 1069.64  4995.5 1067.66
  4995.7 1067.16  4999.2 1067.16  4999.5 1067.66  5002.6 1067.66  5010.1 1068.95
  5030.2 1070.05  5050.2 1070.66  5076.6 1071.92  5081.6 1071.64  5120.3 1073.98
  5130.4 1074.10  5150.4 1075.95  5170.4 1076.47  5190.5 1077.54  5210.5 1078.84
  5220.5 1080.16  5242.7 1080.75  5270.6 1082.32  5290.7 1083.96  5320.7 1085.89
#Mann=3,-1,0
  4866.7    0.05       0  4995.5    0.05       0  4999.5    0.05       0
Bank Sta=4995.5,4999.5
Exp/Cntr=0.3,0.1

Type RM Length L Ch R = 1,14254,496,496,496
BEGIN DESCRIPTION:
LITTLE LLANO 060 21.0
END DESCRIPTION:
XS GIS Cut Line= 3
      2873355.69     10253253.14      2873408.75     10253472.00
      2873705.70     10253703.13
#Sta/Elev= 30
  4774.8 1076.76  4798.2 1075.24  4826.2 1074.79  4846.8 1073.43  4918.5 1070.13
  4923.6 1070.37  4929.1 1069.36  4960.0 1067.51  4980.6 1065.68  4990.9 1064.48
  4998.0 1062.48  5010.5 1061.42  5010.8 1060.92  5014.3 1060.92  5014.5 1061.42
  5027.0 1061.47  5056.0 1063.33  5090.0 1064.79  5097.6 1065.54  5112.1 1065.85
  5148.2 1068.64  5170.0 1069.33  5184.5 1070.81  5198.9 1070.88  5240.6 1073.71
  5278.2 1075.53  5340.1 1079.20  5369.0 1080.36  5373.1 1081.16  5376.3 1081.16
#Mann=5,-1,0
  4774.8    0.05       0  5010.5    0.05       0  5014.5    0.05       0
  5090.0    0.12       0  5278.2    0.05       0
Bank Sta=5010.5,5014.5
Exp/Cntr=0.3,0.1

Type RM Length L Ch R = 1,13758,389,389,389
BEGIN DESCRIPTION:
LITTLE LLANO 060 20.0
END DESCRIPTION:
XS GIS Cut Line= 3
      2873005.68     10253553.09      2873044.25     10253753.00
      2873305.64     10253853.09
#Sta/Elev= 30
  4796.4 1066.20  4816.8 1064.93  4822.4 1063.39  4827.4 1063.85  4847.3 1062.58
  4888.1 1061.42  4908.5 1059.85  4926.1 1057.05  4931.2 1057.82  4940.1 1057.15
  4959.4 1057.16  4969.6 1056.63  4977.9 1056.05  4983.0 1054.75  4987.9 1054.47
  4988.2 1053.97  4991.7 1053.97  4991.9 1054.47  5003.4 1054.61  5023.0 1056.68
  5070.7 1058.02  5095.4 1059.59  5100.7 1058.48  5108.6 1058.92  5119.3 1056.86
  5130.8 1059.37  5167.8 1061.15  5226.4 1063.13  5240.2 1064.69  5279.9 1066.44
#Mann=5,-1,0
  4796.4    0.05       0  4940.1    0.12       0  4987.9    0.07       0
  4991.9    0.12       0  5167.8    0.05       0
Bank Sta=4987.9,4991.9
Exp/Cntr=0.3,0.1

Type RM Length L Ch R = 1,13369,476,476,476
BEGIN DESCRIPTION:
LITTLE LLANO 060 19.0
END DESCRIPTION:
XS GIS Cut Line= 3
      2872905.66     10253553.14      2872685.25     10253829.00
      2872555.70     10254003.09
#Sta/Elev= 30
  4646.9 1063.17  4654.1 1063.37  4660.5 1062.86  4682.9 1062.43  4689.3 1061.69
  4746.9 1059.10  4774.9 1057.08  4788.5 1056.64  4817.4 1054.38  4825.4 1054.22
  4831.8 1053.22  4846.2 1053.22  4852.0 1052.60  4895.8 1052.30  4953.5 1053.51
  4966.9 1052.77  4984.9 1050.78  4993.1 1049.52  4993.3 1049.02  4996.8 1049.02
  4997.1 1049.52  4999.4 1051.10  5009.5 1051.10  5017.6 1052.80  5024.1 1053.58
  5053.3 1054.60  5080.4 1056.23  5088.8 1057.12  5124.2 1058.32  5217.0 1063.91
#Mann=5,-1,0
  4646.9    0.05       0  4852.0    0.12       0  4984.9    0.05       0
  4993.1    0.05       0  4997.1    0.05       0
Bank Sta=4993.1,4997.1
Exp/Cntr=0.3,0.1

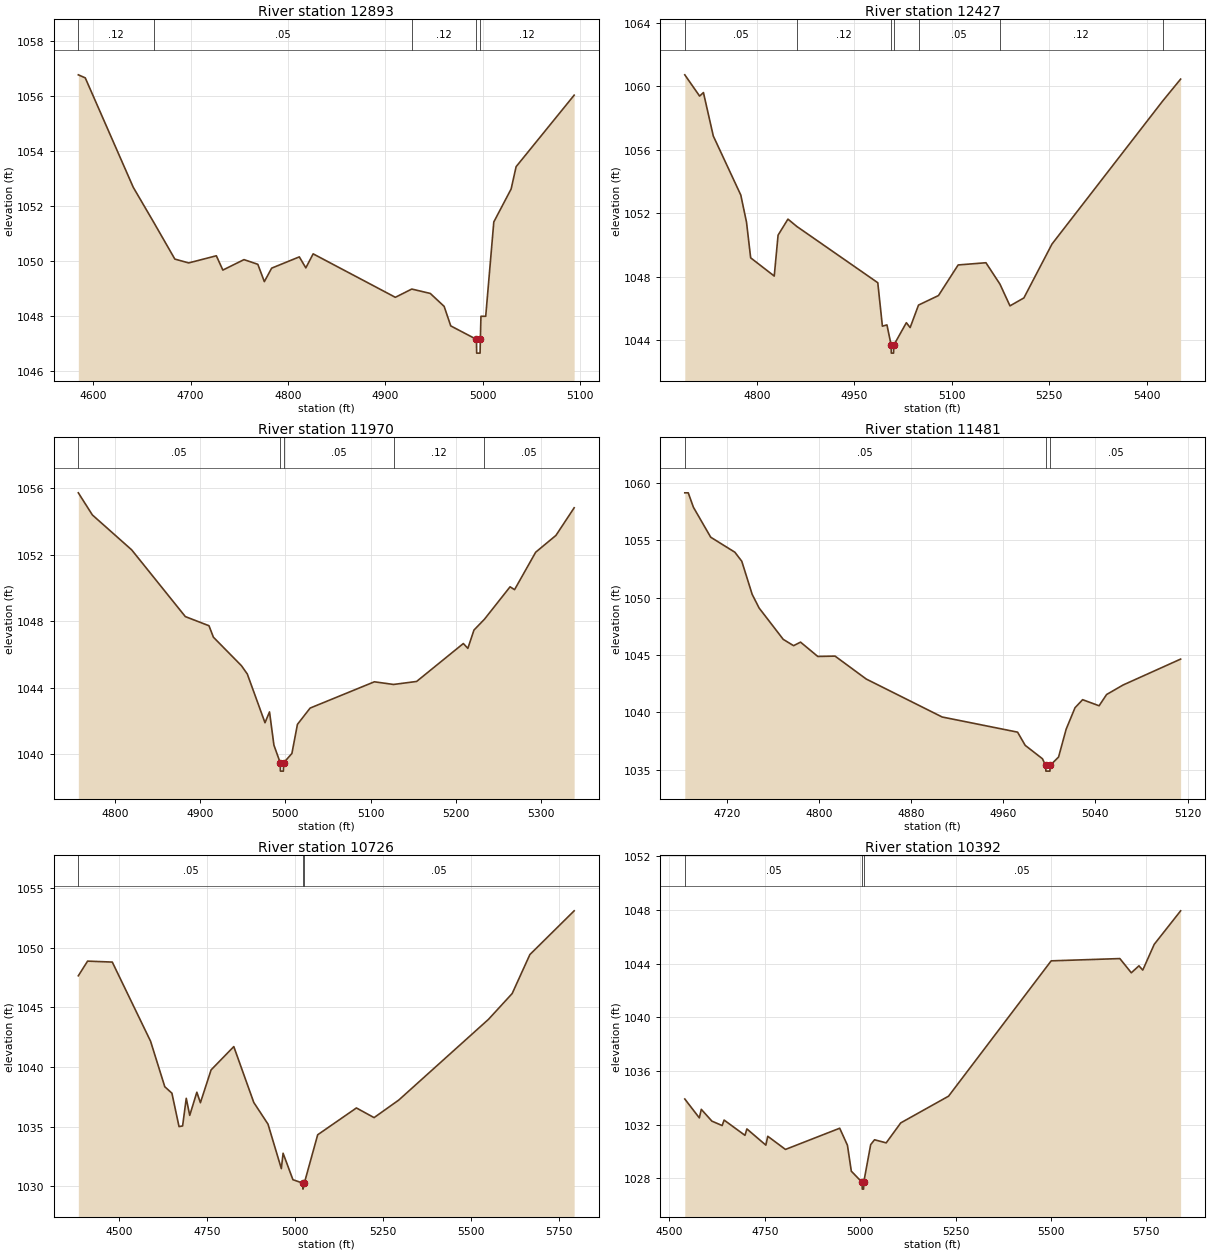
Type RM Length L Ch R = 1,12893,466,466,466
BEGIN DESCRIPTION:
LITTLE LLANO 060 18.0
END DESCRIPTION:
XS GIS Cut Line= 3
      2872655.69     10253403.10      2872378.25     10253712.00
      2872355.68     10253803.15
#Sta/Elev= 30
  4584.8 1056.78  4591.9 1056.67  4641.2 1052.69  4662.0 1051.43  4683.9 1050.08
  4698.1 1049.94  4726.5 1050.20  4733.2 1049.68  4754.9 1050.06  4769.1 1049.89
  4775.8 1049.26  4783.3 1049.75  4811.7 1050.16  4818.4 1049.76  4825.9 1050.27
  4910.3 1048.69  4927.2 1048.99  4946.2 1048.83  4960.4 1048.36  4967.2 1047.65
  4993.6 1047.16  4993.8 1046.66  4997.3 1046.66  4997.6 1047.16  4998.2 1048.00
  5003.1 1048.00  5011.4 1051.43  5029.2 1052.63  5034.3 1053.44  5093.9 1056.04
#Mann=5,-1,0
  4584.8    0.12       0  4662.0    0.05       0  4927.2    0.12       0
  4993.6    0.07       0  4997.6    0.12       0
Bank Sta=4993.6,4997.6
Exp/Cntr=0.3,0.1

Type RM Length L Ch R = 1,12427,457,457,457
BEGIN DESCRIPTION:
LITTLE LLANO 060 17.0
END DESCRIPTION:
XS GIS Cut Line= 3
      2872505.66     10253203.15      2872337.50     10253465.00
      2872105.67     10253853.14
#Sta/Elev= 30
  4688.8 1060.72  4711.6 1059.38  4717.5 1059.60  4732.7 1056.86  4775.0 1053.14
  4783.8 1051.43  4790.2 1049.18  4826.5 1048.03  4832.4 1050.61  4847.6 1051.62
  4861.2 1051.16  4985.9 1047.61  4993.0 1044.87  5000.0 1044.95  5006.5 1043.67
  5006.7 1043.17  5010.2 1043.17  5010.5 1043.67  5029.9 1045.09  5035.7 1044.78
  5048.6 1046.20  5079.3 1046.80  5109.6 1048.73  5152.4 1048.87  5174.0 1047.52
  5189.4 1046.15  5210.8 1046.65  5254.1 1050.05  5424.3 1059.06  5452.1 1060.45
#Mann=7,-1,0
  4688.8    0.05       0  4861.2    0.12       0  5006.5    0.07       0
  5010.5    0.12       0  5048.6    0.05       0  5174.0    0.12       0
  5424.3    0.05       0
Bank Sta=5006.5,5010.5
Exp/Cntr=0.3,0.1

Type RM Length L Ch R = 1,11970,489,489,489
BEGIN DESCRIPTION:
LITTLE LLANO 060 16.0
END DESCRIPTION:
XS GIS Cut Line= 3
      2872005.68     10253203.12      2871935.25     10253436.00
      2872055.68     10253753.10
#Sta/Elev= 30
  4756.7 1055.73  4773.2 1054.40  4819.4 1052.30  4882.4 1048.29  4910.2 1047.74
  4915.4 1047.05  4948.3 1045.34  4955.2 1044.84  4976.0 1041.91  4981.3 1042.56
  4986.5 1040.56  4993.9 1039.50  4994.1 1039.00  4997.6 1039.00  4997.9 1039.50
  5007.6 1040.06  5014.1 1041.81  5029.0 1042.79  5104.5 1044.37  5127.0 1044.21
  5154.1 1044.39  5209.0 1046.67  5214.3 1046.38  5221.5 1047.48  5233.8 1048.13
  5263.9 1050.08  5269.2 1049.91  5294.0 1052.16  5317.8 1053.17  5339.2 1054.83
#Mann=5,-1,0
  4756.7    0.05       0  4993.9    0.05       0  4997.9    0.05       0
  5127.0    0.12       0  5233.8    0.05       0
Bank Sta=4993.9,4997.9
Exp/Cntr=0.3,0.1

Type RM Length L Ch R = 1,11481,755,755,755
BEGIN DESCRIPTION:
LITTLE LLANO 060 15.0
END DESCRIPTION:
XS GIS Cut Line= 3
      2871705.68     10253103.12      2871529.25     10253366.00
      2871455.70     10253453.10
#Sta/Elev= 30
  4683.4 1059.15  4686.4 1059.15  4690.9 1057.89  4705.9 1055.28  4726.9 1053.97
  4732.9 1053.18  4741.9 1050.30  4747.9 1049.11  4768.9 1046.37  4777.9 1045.82
  4783.9 1046.13  4798.9 1044.88  4813.9 1044.91  4841.0 1042.91  4906.9 1039.60
  4972.4 1038.28  4979.0 1037.13  4994.0 1035.96  4996.7 1035.38  4997.0 1034.88
  5000.5 1034.88  5000.7 1035.38  5008.0 1036.11  5014.6 1038.54  5022.3 1040.41
  5028.9 1041.11  5043.2 1040.58  5049.7 1041.56  5064.0 1042.39  5114.0 1044.65
#Mann=3,-1,0
  4683.4    0.05       0  4996.7    0.03       0  5000.7    0.05       0
Bank Sta=4996.7,5000.7
Exp/Cntr=0.3,0.1

Type RM Length L Ch R = 1,10726,334,334,334
BEGIN DESCRIPTION:
Mapping XS 29870bfa
END DESCRIPTION:
XS GIS Cut Line= 4
      2870947.16     10252320.16      2871038.31     10252945.20
      2871025.29     10253400.93      2871168.50     10253687.35
#Sta/Elev= 30
  4385.3 1047.66  4411.6 1048.89  4481.7 1048.81  4590.4 1042.17  4630.8 1038.35
  4651.0 1037.81  4671.2 1035.01  4681.4 1035.06  4691.7 1037.38  4701.6 1035.95
  4721.8 1037.89  4731.9 1037.01  4762.2 1039.76  4826.7 1041.72  4883.5 1037.03
  4923.9 1035.21  4961.7 1031.48  4966.7 1032.77  4994.6 1030.55  5022.9 1030.26
  5023.1 1029.76  5026.9 1030.26  5064.9 1034.32  5174.9 1036.57  5225.0 1035.76
  5295.0 1037.23  5550.0 1044.01  5617.1 1046.17  5667.4 1049.44  5793.1 1053.11
#Mann=3,-1,0
  4385.3    0.05       0  5022.9    0.05       0  5026.9    0.05       0
Bank Sta=5022.9,5026.9
Exp/Cntr=0.3,0.1

Type RM Length L Ch R = 1,10392,786,786,786
BEGIN DESCRIPTION:
Mapping XS 79ebeefb
END DESCRIPTION:
XS GIS Cut Line= 3
      2870673.72     10252333.19      2870790.91     10253010.31
      2870790.91     10253622.32
#Sta/Elev= 30
  4540.6 1033.91  4578.7 1032.50  4583.8 1033.14  4611.6 1032.26  4638.5 1031.93
  4643.6 1032.34  4698.3 1031.20  4703.3 1031.68  4753.0 1030.47  4758.0 1031.13
  4804.4 1030.15  4946.5 1031.73  4966.8 1030.46  4976.9 1028.53  5005.4 1027.69
  5005.6 1027.19  5009.1 1027.19  5009.4 1027.69  5027.7 1030.51  5037.8 1030.87
  5068.3 1030.64  5106.5 1032.13  5231.7 1034.12  5500.6 1044.21  5680.6 1044.38
  5710.6 1043.32  5730.6 1043.84  5740.6 1043.52  5770.6 1045.44  5839.8 1047.94
#Mann=3,-1,0
  4540.6    0.05       0  5005.4    0.05       0  5009.4    0.05       0
Bank Sta=5005.4,5009.4
Exp/Cntr=0.3,0.1

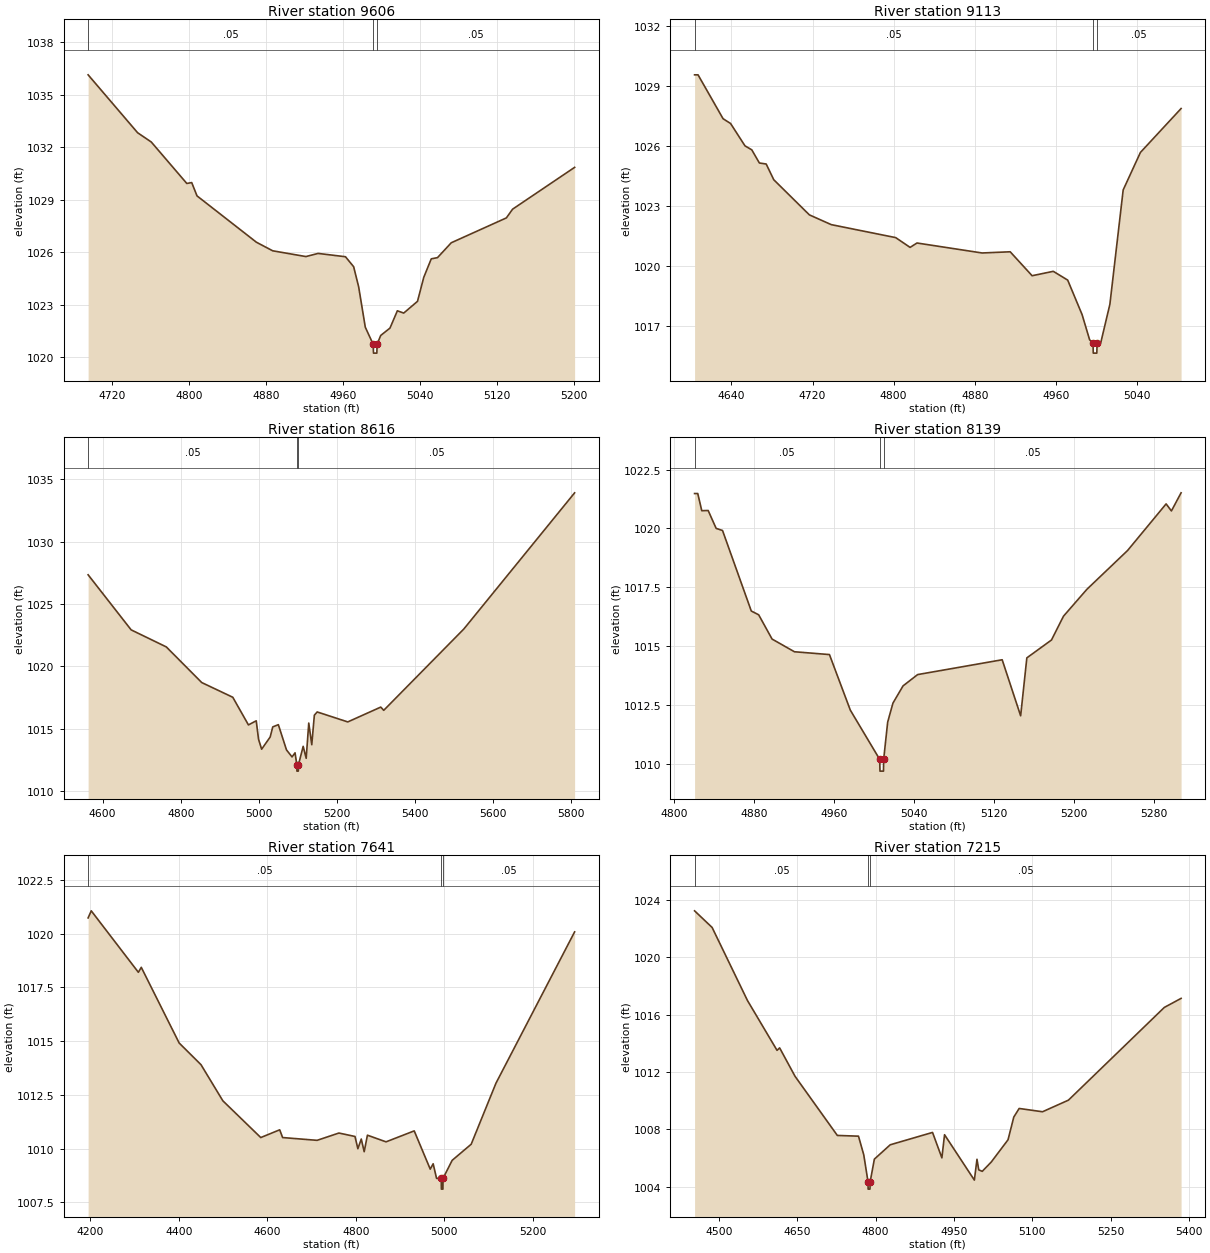
Type RM Length L Ch R = 1,9606,493,493,493
BEGIN DESCRIPTION:
LITTLE LLANO 060 11.0
END DESCRIPTION:
XS GIS Cut Line= 3
      2870655.64     10252153.12      2870359.50     10252224.00
      2870205.70     10252353.10
#Sta/Elev= 30
  4695.5 1036.15  4746.9 1032.84  4761.1 1032.31  4798.0 1029.94  4803.1 1029.99
  4808.6 1029.23  4870.3 1026.58  4887.2 1026.09  4921.7 1025.76  4934.4 1025.94
  4962.8 1025.75  4971.3 1025.18  4976.5 1024.03  4983.4 1021.72  4991.6 1020.74
  4991.9 1020.24  4995.4 1020.24  4995.6 1020.74  4999.4 1021.25  5009.0 1021.67
  5016.7 1022.66  5023.3 1022.53  5037.6 1023.20  5044.1 1024.57  5051.9 1025.63
  5058.4 1025.70  5072.7 1026.55  5129.9 1027.97  5136.4 1028.47  5200.8 1030.86
#Mann=3,-1,0
  4695.5    0.05       0  4991.6    0.05       0  4995.6    0.05       0
Bank Sta=4991.6,4995.6
Exp/Cntr=0.3,0.1

Type RM Length L Ch R = 1,9113,497,497,497
BEGIN DESCRIPTION:
LITTLE LLANO 060 10.0
END DESCRIPTION:
XS GIS Cut Line= 3
      2870255.70     10251753.10      2869962.75     10252020.00
      2869955.69     10252103.10
#Sta/Elev= 30
  4603.7 1029.57  4607.1 1029.57  4631.8 1027.37  4639.2 1027.13  4653.4 1026.01
  4660.1 1025.81  4667.6 1025.15  4674.3 1025.10  4681.8 1024.31  4716.9 1022.55
  4738.5 1022.06  4802.0 1021.41  4816.2 1020.92  4823.0 1021.14  4887.2 1020.64
  4914.9 1020.70  4936.5 1019.50  4957.4 1019.72  4971.6 1019.28  4985.8 1017.55
  4993.2 1016.29  4996.6 1016.12  4996.8 1015.62  5000.3 1015.62  5000.6 1016.12
  5004.1 1016.12  5013.2 1018.07  5026.3 1023.80  5043.3 1025.68  5083.4 1027.88
#Mann=3,-1,0
  4603.7    0.05       0  4996.6    0.05       0  5000.6    0.05       0
Bank Sta=4996.6,5000.6
Exp/Cntr=0.3,0.1

Type RM Length L Ch R = 1,8616,477,477,477
BEGIN DESCRIPTION:
LITTLE LLANO 060 9.0
END DESCRIPTION:
XS GIS Cut Line= 3
      2870105.70     10251603.11      2869669.00     10251626.00
      2869055.69     10252153.11
#Sta/Elev= 30
  4562.7 1027.35  4672.9 1022.93  4763.0 1021.56  4853.7 1018.70  4933.2 1017.52
  4973.3 1015.30  4993.3 1015.63  4999.2 1014.15  5007.1 1013.35  5029.0 1014.33
  5035.6 1015.14  5049.9 1015.32  5070.8 1013.29  5085.0 1012.73  5092.7 1013.06
  5097.3 1012.09  5097.5 1011.59  5101.0 1011.59  5101.3 1012.09  5113.5 1013.58
  5121.2 1012.62  5127.8 1015.45  5135.5 1013.71  5142.1 1016.08  5149.4 1016.34
  5227.7 1015.54  5312.2 1016.73  5319.8 1016.47  5525.0 1023.00  5808.7 1033.93
#Mann=3,-1,0
  4562.7    0.05       0  5097.3    0.05       0  5101.3    0.05       0
Bank Sta=5097.3,5101.3
Exp/Cntr=0.3,0.1

Type RM Length L Ch R = 1,8139,498,498,498
BEGIN DESCRIPTION:
LITTLE LLANO 060 8.0
END DESCRIPTION:
XS GIS Cut Line= 3
      2869455.69     10251453.11      2869315.75     10251566.00
      2869205.68     10251853.12
#Sta/Elev= 30
  4820.2 1021.48  4823.4 1021.48  4827.4 1020.75  4833.8 1020.76  4841.8 1020.00
  4848.2 1019.91  4877.0 1016.49  4884.4 1016.33  4897.8 1015.30  4920.2 1014.76
  4955.3 1014.64  4976.2 1012.28  5005.6 1010.19  5005.9 1009.69  5009.4 1009.69
  5009.6 1010.19  5013.6 1011.77  5018.9 1012.58  5029.0 1013.31  5043.6 1013.79
  5128.3 1014.42  5146.8 1012.04  5153.0 1014.50  5177.7 1015.26  5189.7 1016.27
  5213.1 1017.41  5253.9 1019.06  5292.5 1021.04  5297.8 1020.74  5307.5 1021.51
#Mann=3,-1,0
  4820.2    0.05       0  5005.6    0.05       0  5009.6    0.05       0
Bank Sta=5005.6,5009.6
Exp/Cntr=0.3,0.1

Type RM Length L Ch R = 1,7641,426,426,426
BEGIN DESCRIPTION:
LITTLE LLANO 060 7.0
END DESCRIPTION:
XS GIS Cut Line= 3
      2869605.68     10250753.12      2868993.75     10251276.00
      2868805.67     10251503.13
#Sta/Elev= 30
  4195.1 1020.73  4202.2 1021.06  4308.7 1018.20  4315.3 1018.43  4400.9 1014.91
  4450.3 1013.90  4499.7 1012.22  4585.4 1010.51  4628.2 1010.87  4634.8 1010.51
  4712.7 1010.38  4762.1 1010.72  4798.4 1010.56  4804.9 1009.99  4812.6 1010.44
  4819.2 1009.85  4826.5 1010.62  4868.6 1010.31  4932.3 1010.82  4968.5 1009.04
  4975.1 1009.29  4982.8 1008.61  4993.4 1008.61  4993.7 1008.11  4997.2 1008.11
  4997.4 1008.61  5018.1 1009.45  5061.1 1010.20  5117.1 1013.04  5294.9 1020.08
#Mann=3,-1,0
  4195.1    0.05       0  4993.4    0.03       0  4997.4    0.05       0
Bank Sta=4993.4,4997.4
Exp/Cntr=0.3,0.1

Type RM Length L Ch R = 1,7215,485,485,485
BEGIN DESCRIPTION:
LITTLE LLANO 060 6.0
END DESCRIPTION:
XS GIS Cut Line= 3
      2868755.69     10250403.12      2868841.75     10250943.00
      2868705.67     10251303.15
#Sta/Elev= 30
  4453.3 1023.23  4486.9 1022.07  4554.6 1016.98  4611.2 1013.51  4616.2 1013.68
  4645.7 1011.70  4726.7 1007.58  4767.2 1007.53  4777.3 1006.23  4785.5 1004.34
  4785.7 1003.84  4789.2 1003.84  4789.5 1004.34  4797.6 1005.93  4828.0 1006.93
  4909.0 1007.79  4926.9 1006.02  4932.0 1007.63  4989.1 1004.47  4994.1 1005.92
  4997.5 1005.18  5004.2 1005.08  5021.5 1005.73  5053.6 1007.28  5064.6 1008.86
  5074.9 1009.46  5119.6 1009.23  5169.3 1010.04  5352.9 1016.50  5385.0 1017.13
#Mann=3,-1,0
  4453.3    0.05       0  4785.5    0.05       0  4789.5    0.05       0
Bank Sta=4785.5,4789.5
Exp/Cntr=0.3,0.1

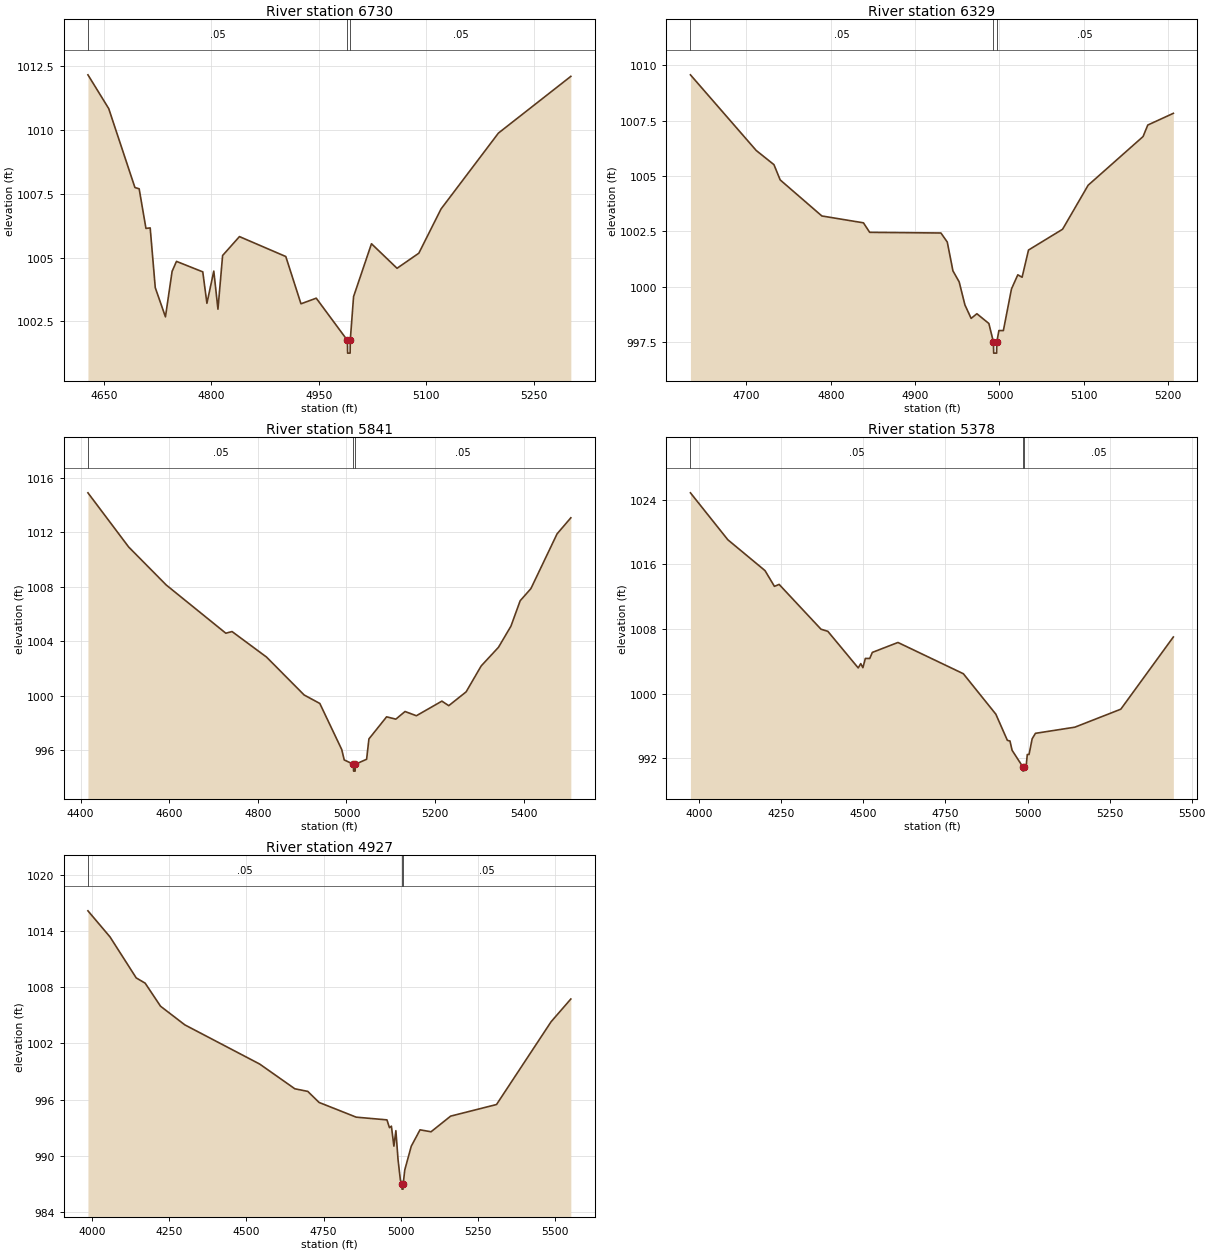
Type RM Length L Ch R = 1,6730,401,401,401
BEGIN DESCRIPTION:
LITTLE LLANO 060 5.0
END DESCRIPTION:
XS GIS Cut Line= 3
      2868605.68     10250553.12      2868410.25     10250870.00
      2868305.69     10251153.11
#Sta/Elev= 30
  4627.7 1012.15  4656.7 1010.83  4693.3 1007.74  4699.2 1007.69  4708.7 1006.14
  4714.6 1006.16  4721.7 1003.82  4735.9 1002.68  4745.2 1004.46  4751.3 1004.85
  4788.0 1004.44  4793.8 1003.21  4803.4 1004.47  4809.2 1002.98  4815.7 1005.08
  4839.2 1005.82  4903.9 1005.04  4925.1 1003.19  4946.4 1003.41  4989.9 1001.76
  4990.2 1001.26  4993.7 1001.26  4993.9 1001.76  4998.5 1003.47  5023.5 1005.54
  5059.2 1004.58  5089.6 1005.17  5120.6 1006.90  5200.7 1009.87  5301.8 1012.09
#Mann=3,-1,0
  4627.7    0.05       0  4989.9    0.05       0  4993.9    0.05       0
Bank Sta=4989.9,4993.9
Exp/Cntr=0.3,0.1

Type RM Length L Ch R = 1,6329,488,488,488
BEGIN DESCRIPTION:
LITTLE LLANO 060 4.0
END DESCRIPTION:
XS GIS Cut Line= 3
      2868305.66     10250503.13      2868034.00     10250749.00
      2868005.68     10250953.14
#Sta/Elev= 30
  4633.6 1009.57  4711.6 1006.15  4732.6 1005.51  4740.0 1004.82  4789.4 1003.19
  4838.7 1002.88  4846.1 1002.45  4930.6 1002.42  4938.1 1002.01  4944.8 1000.71
  4952.2 1000.21  4959.0  999.17  4966.4  998.56  4973.2  998.77  4987.4  998.33
  4992.8  997.49  4993.1  996.99  4996.6  996.99  4996.8  997.49  4999.3  998.01
  5004.6  998.01  5014.2  999.89  5021.7 1000.53  5026.8 1000.42  5034.4 1001.65
  5074.8 1002.59  5105.1 1004.58  5170.2 1006.78  5175.8 1007.30  5206.1 1007.83
#Mann=3,-1,0
  4633.6    0.05       0  4992.8    0.05       0  4996.8    0.05       0
Bank Sta=4992.8,4996.8
Exp/Cntr=0.3,0.1

Type RM Length L Ch R = 1,5841,463,463,463
BEGIN DESCRIPTION:
LITTLE LLANO 060 3.0
END DESCRIPTION:
XS GIS Cut Line= 3
      2868155.67     10250003.12      2867743.50     10250416.00
      2867605.69     10250903.08
#Sta/Elev= 30
  4416.6 1014.88  4508.5 1010.91  4593.4 1008.12  4727.7 1004.59  4741.8 1004.71
  4819.6 1002.84  4904.5 1000.06  4939.8  999.44  4989.3  996.06  4994.9  995.30
  5015.8  994.98  5016.0  994.48  5019.5  994.48  5019.8  994.98  5045.4  995.35
  5050.6  996.84  5090.5  998.46  5111.3  998.29  5132.1  998.85  5157.7  998.54
  5215.2  999.61  5230.8  999.28  5269.9 1000.29  5303.9 1002.19  5343.0 1003.56
  5371.1 1005.11  5391.9 1006.97  5416.1 1007.86  5475.1 1011.87  5506.2 1013.05
#Mann=3,-1,0
  4416.6    0.05       0  5015.8    0.05       0  5019.8    0.05       0
Bank Sta=5015.8,5019.8
Exp/Cntr=0.3,0.1

Type RM Length L Ch R = 1,5378,451,451,451
BEGIN DESCRIPTION:
LITTLE LLANO 060 2.0
END DESCRIPTION:
XS GIS Cut Line= 3
      2868105.66     10249653.13      2867315.50     10250309.00
      2867305.68     10250753.09
#Sta/Elev= 30
  3973.1 1024.86  4087.0 1019.05  4200.3 1015.23  4229.0 1013.28  4243.3 1013.52
  4370.9 1007.97  4391.7 1007.71  4484.2 1003.18  4492.0 1003.71  4498.5 1003.21
  4505.9 1004.35  4519.3 1004.35  4527.2 1005.10  4605.3 1006.33  4804.5 1002.46
  4903.5  997.45  4938.6  994.21  4946.5  994.13  4953.0  992.98  4986.1  990.90
  4986.3  990.40  4990.2  990.90  4995.9  991.05  4999.3  992.46  5004.6  992.46
  5014.1  994.40  5024.1  995.08  5144.1  995.84  5284.2  998.07  5444.2 1007.01
#Mann=3,-1,0
  3973.1    0.05       0  4986.1    0.05       0  4990.2    0.05       0
Bank Sta=4986.1,4990.2
Exp/Cntr=0.3,0.1

Type RM Length L Ch R = 1,4927,0,0,0
BEGIN DESCRIPTION:
LITTLE LLANO 060 1.0
END DESCRIPTION:
XS GIS Cut Line= 3
      2867505.71     10249553.08      2866880.50     10250350.00
      2867255.69     10250753.12
#Sta/Elev= 30
  3987.1 1016.15  4058.5 1013.37  4143.5 1008.99  4172.4 1008.43  4222.2 1005.97
  4300.8 1003.98  4543.1  999.80  4657.0  997.16  4698.9  996.88  4735.6  995.70
  4855.8  994.13  4955.3  993.84  4963.4  993.01  4969.7  993.17  4977.8  991.04
  4984.2  992.69  4991.2  989.60  4998.7  987.45  5003.6  986.95  5003.9  986.45
  5007.5  986.45  5007.7  986.95  5013.0  988.50  5034.0  991.03  5062.4  992.78
  5098.0  992.57  5161.5  994.24  5310.1  995.48  5486.9 1004.32  5550.7 1006.74
#Mann=3,-1,0
  3987.1    0.05       0  5003.6    0.05       0  5007.7    0.05       0
Bank Sta=5003.6,5007.7
Exp/Cntr=0.3,0.1

Chan Stop Cuts=-1