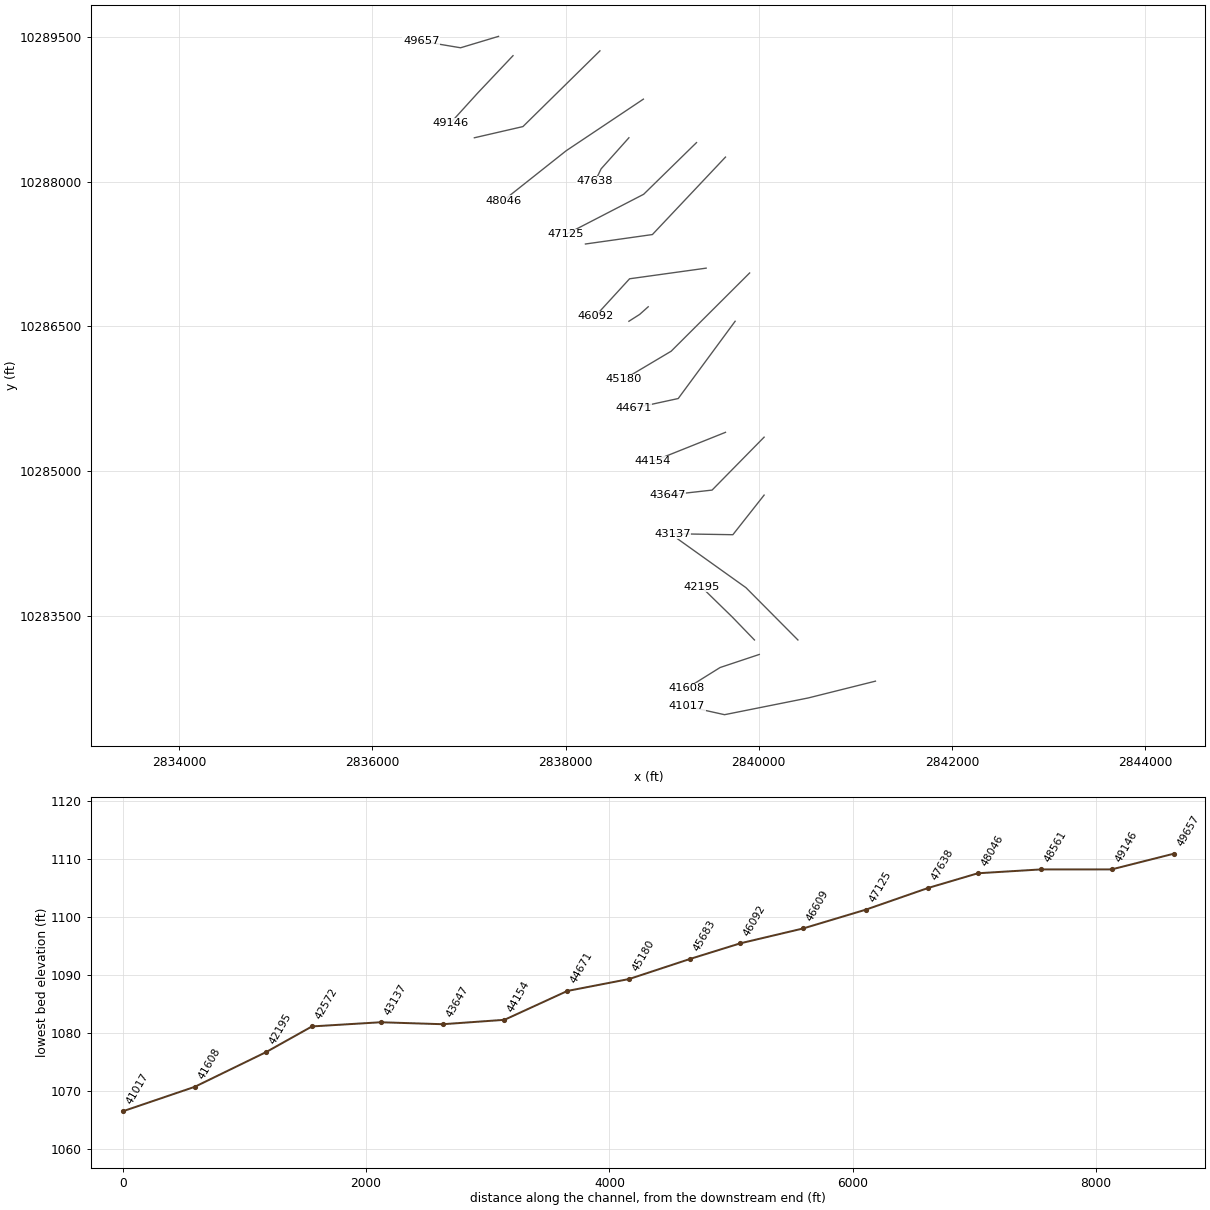
HEC-RAS study LITTLE LLANO RIVER.prj: LITTLE LLANO RIVER Base Level Engineering

--- LITTLE LLANO RIVER.g01 (geometry) --- (continued)

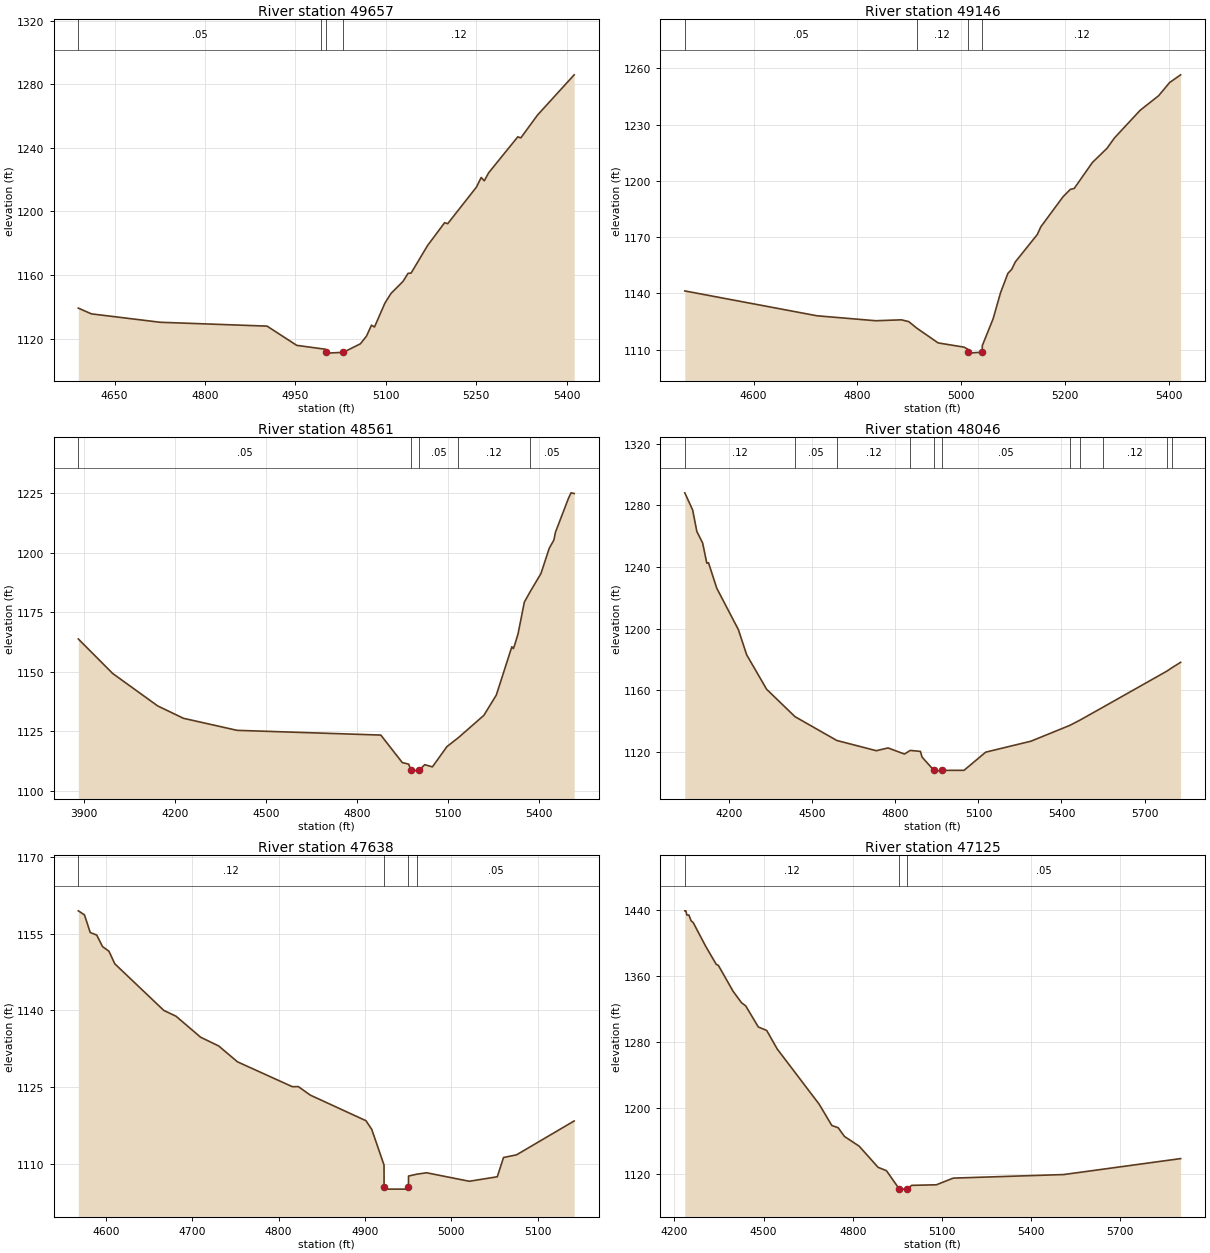
Type RM Length L Ch R = 1,49657,511,511,511
BEGIN DESCRIPTION:
LITTLE LLANO RIVER 92.0
END DESCRIPTION:
XS GIS Cut Line= 3
      2837305.68     10289503.11      2836912.75     10289385.00
      2836505.71     10289453.11
#Sta/Elev= 30
  4589.7 1139.22  4611.4 1135.60  4725.4 1130.32  4903.0 1127.89  4952.2 1115.80
  4992.0 1113.75  5000.0 1113.35  5001.5 1111.41  5002.0 1110.91  5029.5 1111.41
  5057.9 1116.78  5068.0 1121.60  5076.3 1128.48  5081.3 1127.35  5098.4 1142.22
  5108.6 1148.41  5128.8 1156.11  5137.0 1161.09  5142.0 1161.22  5169.4 1178.58
  5197.7 1192.93  5202.8 1192.31  5250.5 1215.31  5258.4 1221.37  5263.5 1219.27
  5270.8 1224.31  5319.1 1246.90  5324.2 1246.29  5351.9 1260.62  5412.7 1285.91
#Mann=4,-1,0
  4589.7    0.05       0  4992.0    0.12       0  5001.5    0.07       0
  5029.5    0.12       0
Bank Sta=5001.5,5029.5
Exp/Cntr=0.3,0.1

Type RM Length L Ch R = 1,49146,585,585,585
BEGIN DESCRIPTION:
LITTLE LLANO RIVER 91.0
END DESCRIPTION:
XS GIS Cut Line= 3
      2837455.69     10289303.12      2837089.75     10288916.00
      2836805.69     10288603.11
#Sta/Elev= 30
  4467.3 1141.36  4722.0 1128.11  4835.2 1125.47  4884.6 1125.95  4898.8 1125.00
  4914.5 1121.47  4955.4 1113.65  5005.3 1111.39  5012.1 1110.36  5012.3 1108.70
  5012.8 1108.20  5040.3 1108.70  5040.5 1112.21  5061.4 1126.57  5075.6 1140.36
  5089.8 1150.73  5097.2 1152.89  5104.0 1156.78  5146.5 1171.46  5153.3 1175.55
  5195.9 1191.51  5210.1 1195.50  5217.5 1195.97  5252.6 1209.82  5281.0 1217.47
  5295.2 1222.94  5344.5 1237.62  5380.4 1245.47  5401.3 1252.42  5422.6 1256.56
#Mann=4,-1,0
  4467.3    0.05       0  4914.5    0.12       0  5012.3    0.07       0
  5040.3    0.12       0
Bank Sta=5012.3,5040.3
Exp/Cntr=0.3,0.1

Type RM Length L Ch R = 1,48561,515,515,515
BEGIN DESCRIPTION:
LITTLE LLANO RIVER 90.0
END DESCRIPTION:
XS GIS Cut Line= 3
      2838355.70     10289353.12      2837558.50     10288569.00
      2837055.68     10288453.11
#Sta/Elev= 30
  3881.8 1163.72  3994.9 1149.24  4143.5 1135.58  4228.3 1130.39  4405.1 1125.33
  4878.8 1123.34  4949.5 1111.79  4970.8 1111.12  4977.9 1108.69  4978.4 1108.19
  5006.0 1108.69  5023.4 1110.90  5048.8 1109.98  5096.7 1118.50  5134.2 1122.23
  5218.4 1131.63  5259.4 1140.14  5310.6 1160.44  5315.8 1159.68  5321.0 1161.62
  5331.3 1166.02  5351.8 1179.21  5371.3 1183.66  5406.5 1191.20  5433.9 1201.84
  5449.3 1205.34  5454.4 1208.59  5497.2 1222.83  5505.7 1225.14  5516.0 1224.86
#Mann=5,-1,0
  3881.8    0.05       0  4977.9    0.03       0  5006.0    0.05       0
  5134.2    0.12       0  5371.3    0.05       0
Bank Sta=4977.9,5006
Exp/Cntr=0.3,0.1

Type RM Length L Ch R = 1,48046,408,408,408
BEGIN DESCRIPTION:
LITTLE LLANO RIVER 89.0
END DESCRIPTION:
XS GIS Cut Line= 3
      2838805.66     10288853.09      2838006.50     10288319.00
      2837355.67     10287803.10
#Sta/Elev= 30
  4038.8 1288.22  4067.3 1277.03  4082.3 1263.15  4103.3 1255.65  4118.3 1242.56
  4124.4 1242.87  4154.4 1226.26  4232.5 1199.37  4262.5 1183.01  4334.6 1160.66
  4437.1 1142.88  4588.2 1127.43  4731.0 1120.79  4773.1 1122.59  4832.6 1118.62
  4853.3 1120.97  4890.2 1120.35  4896.2 1116.65  4939.1 1108.03  4939.6 1107.53
  4967.3 1108.03  5047.7 1108.05  5126.2 1119.85  5289.7 1126.97  5430.1 1137.23
  5465.9 1140.56  5549.8 1149.02  5781.0 1172.47  5799.5 1174.71  5830.5 1178.18
#Mann=11,-1,0
  4038.8    0.12       0  4437.1    0.05       0  4588.2    0.12       0
  4853.3    0.05       0  4939.1    0.03       0  4967.3    0.05       0
  5430.1    0.12       0  5465.9    0.05       0  5549.8    0.12       0
  5781.0    0.05       0  5799.5    0.12       0
Bank Sta=4939.1,4967.3
Exp/Cntr=0.3,0.1

Type RM Length L Ch R = 1,47638,513,513,513
BEGIN DESCRIPTION:
LITTLE LLANO RIVER 88.0
END DESCRIPTION:
XS GIS Cut Line= 3
      2838655.65     10288453.08      2838367.75     10288131.00
      2838305.66     10288003.07
#Sta/Elev= 30
  4568.0 1159.46  4575.1 1158.67  4581.8 1155.21  4589.3 1154.72  4596.0 1152.47
  4603.5 1151.55  4610.2 1149.10  4667.0 1139.97  4681.2 1138.83  4709.6 1134.73
  4730.6 1133.01  4752.3 1129.91  4815.8 1125.05  4822.8 1125.06  4836.7 1123.39
  4901.1 1118.39  4907.8 1116.69  4922.0 1109.72  4922.1 1105.50  4922.6 1105.00
  4949.8 1105.00  4950.3 1105.50  4950.4 1107.56  4960.2 1107.93  4971.3 1108.20
  5020.8 1106.54  5053.2 1107.42  5060.4 1111.19  5075.5 1111.71  5142.2 1118.34
#Mann=4,-1,0
  4568.0    0.12       0  4922.1    0.03       0  4950.3    0.12       0
  4960.2    0.05       0
Bank Sta=4922.1,4950.3
Exp/Cntr=0.3,0.1

Type RM Length L Ch R = 1,47125,516,516,516
BEGIN DESCRIPTION:
LITTLE LLANO RIVER 87.0
END DESCRIPTION:
XS GIS Cut Line= 3
      2839355.65     10288403.08      2838808.50     10287868.00
      2838005.67     10287453.10
#Sta/Elev= 30
  4234.7 1439.31  4238.2 1439.31  4241.7 1434.21  4248.7 1434.14  4255.9 1427.21
  4262.9 1425.12  4305.3 1396.06  4340.7 1374.25  4347.7 1373.07  4397.3 1341.59
  4425.6 1327.71  4439.8 1323.82  4482.2 1298.23  4510.5 1293.96  4545.8 1271.49
  4687.2 1204.33  4729.6 1178.58  4750.9 1175.85  4772.1 1165.23  4821.7 1153.43
  4885.2 1127.79  4913.5 1123.67  4956.0 1101.75  4956.5 1101.25  4984.2 1101.75
  4998.4 1105.83  5081.6 1106.52  5138.2 1114.61  5509.7 1118.94  5903.7 1138.33
#Mann=3,-1,0
  4234.7    0.12       0  4956.0    0.03       0  4984.2    0.05       0
Bank Sta=4956,4984.2
Exp/Cntr=0.3,0.1

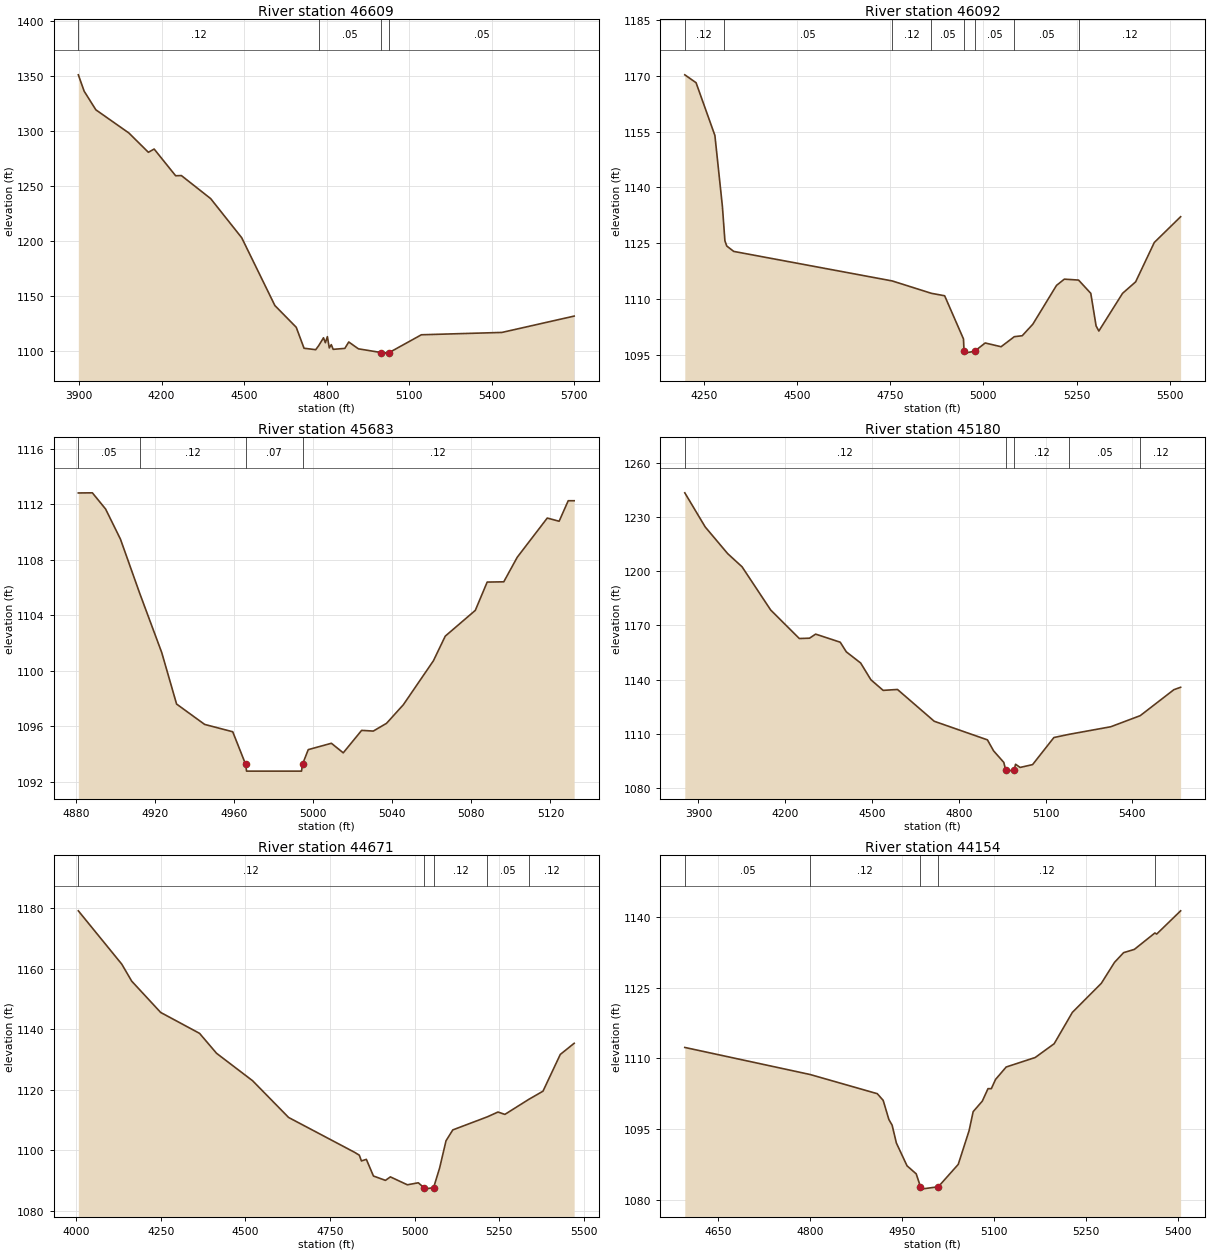
Type RM Length L Ch R = 1,46609,517,517,517
BEGIN DESCRIPTION:
LITTLE LLANO RIVER 86.0
END DESCRIPTION:
XS GIS Cut Line= 3
      2839655.68     10288253.11      2838899.00     10287451.00
      2838205.68     10287353.11
#Sta/Elev= 30
  3897.3 1351.36  3918.5 1336.46  3961.0 1319.52  4081.2 1298.38  4152.0 1280.84
  4173.0 1283.79  4251.1 1259.48  4272.1 1259.64  4378.5 1238.66  4491.4 1203.04
  4612.0 1141.32  4689.6 1121.54  4718.0 1102.44  4760.4 1101.13  4771.5 1104.89
  4788.8 1111.96  4795.6 1107.48  4802.9 1113.00  4809.8 1102.71  4817.1 1105.73
  4824.0 1101.44  4866.4 1102.31  4880.6 1108.14  4915.8 1101.91  4999.3 1098.50
  4999.8 1098.00  5027.6 1098.50  5144.7 1114.71  5437.6 1116.84  5700.2 1131.71
#Mann=4,-1,0
  3897.3    0.12       0  4771.5    0.05       0  4999.3    0.03       0
  5027.6    0.05       0
Bank Sta=4999.3,5027.6
Exp/Cntr=0.3,0.1

Type RM Length L Ch R = 1,46092,409,409,409
BEGIN DESCRIPTION:
LITTLE LLANO RIVER 85.0
END DESCRIPTION:
XS GIS Cut Line= 3
      2839455.64     10287103.11      2838662.75     10286993.00
      2838305.67     10286603.10
#Sta/Elev= 30
  4199.5 1170.29  4229.7 1168.17  4280.2 1153.97  4300.4 1134.82  4304.1 1129.68
  4307.0 1125.66  4312.0 1124.24  4330.7 1122.79  4755.5 1114.85  4860.5 1111.52
  4896.1 1110.86  4946.6 1099.24  4948.1 1095.93  4948.6 1095.43  4976.4 1095.93
  5004.8 1098.16  5047.4 1097.15  5082.8 1099.85  5104.1 1100.11  5132.5 1103.21
  5196.0 1113.65  5217.0 1115.33  5255.1 1115.08  5287.9 1111.51  5302.1 1102.75
  5309.5 1101.38  5373.0 1111.51  5408.1 1114.60  5458.1 1125.19  5528.7 1132.12
#Mann=8,-1,0
  4199.5    0.12       0  4304.1    0.05       0  4755.5    0.12       0
  4860.5    0.05       0  4948.1    0.07       0  4976.4    0.05       0
  5082.8    0.05       0  5255.1    0.12       0
Bank Sta=4948.1,4976.4
Exp/Cntr=0.3,0.1

Type RM Length L Ch R = 1,45683,503,503,503
BEGIN DESCRIPTION:
LITTLE LLANO RIVER 84.0
END DESCRIPTION:
XS GIS Cut Line= 3
      2838855.65     10286703.08      2838767.00     10286624.00
      2838655.66     10286553.10
#Sta/Elev= 30
  4881.2 1112.83  4888.3 1112.84  4895.0 1111.67  4902.5 1109.50  4912.3 1105.57
  4923.4 1101.31  4930.9 1097.60  4945.1 1096.13  4959.3 1095.60  4965.8 1093.26
  4966.3 1092.76  4994.1 1092.76  4994.6 1093.26  4997.5 1094.31  5009.2 1094.77
  5015.2 1094.08  5024.5 1095.70  5030.4 1095.65  5037.1 1096.21  5045.6 1097.55
  5060.8 1100.72  5066.8 1102.50  5082.0 1104.36  5088.0 1106.40  5096.4 1106.42
  5103.2 1108.19  5118.4 1111.02  5124.4 1110.79  5129.0 1112.27  5132.0 1112.27
#Mann=4,-1,0
  4881.2    0.05       0  4912.3    0.12       0  4965.8    0.07       0
  4994.6    0.12       0
Bank Sta=4965.8,4994.6
Exp/Cntr=0.3,0.1

Type RM Length L Ch R = 1,45180,509,509,509
BEGIN DESCRIPTION:
LITTLE LLANO RIVER 83.0
END DESCRIPTION:
XS GIS Cut Line= 3
      2839905.67     10287053.10      2839093.25     10286243.00
      2838605.71     10285953.13
#Sta/Elev= 30
  3852.7 1243.36  3923.4 1224.44  4001.2 1209.66  4050.7 1202.41  4149.7 1178.48
  4248.7 1162.70  4284.0 1162.88  4305.2 1165.13  4390.1 1160.66  4411.3 1155.30
  4460.8 1149.14  4496.2 1139.86  4538.6 1133.99  4588.1 1134.49  4715.3 1116.88
  4899.2 1106.59  4920.4 1100.52  4955.8 1094.11  4962.5 1089.78  4963.0 1089.28
  4991.4 1089.78  4996.4 1093.09  5012.1 1091.32  5055.3 1092.89  5129.0 1107.88
  5181.9 1109.67  5325.7 1113.85  5427.5 1119.99  5544.0 1134.38  5567.2 1135.70
#Mann=5,-1,0
  3852.7    0.12       0  4962.5    0.07       0  4991.4    0.12       0
  5181.9    0.05       0  5427.5    0.12       0
Bank Sta=4962.5,4991.4
Exp/Cntr=0.3,0.1

Type RM Length L Ch R = 1,44671,517,517,517
BEGIN DESCRIPTION:
LITTLE LLANO RIVER 82.0
END DESCRIPTION:
XS GIS Cut Line= 3
      2839755.69     10286553.12      2839166.25     10285753.00
      2838705.66     10285653.11
#Sta/Elev= 30
  4006.2 1179.04  4134.6 1161.44  4163.9 1155.84  4249.5 1145.51  4364.5 1138.60
  4414.6 1132.03  4521.1 1122.98  4627.5 1110.86  4821.8 1099.40  4836.5 1098.41
  4842.7 1096.51  4857.3 1097.03  4878.2 1091.54  4913.7 1090.10  4928.3 1091.25
  4978.4 1088.64  5010.8 1089.30  5027.1 1087.71  5027.6 1087.21  5056.0 1087.71
  5073.8 1094.20  5092.7 1103.17  5112.7 1106.75  5215.1 1111.08  5246.2 1112.65
  5266.6 1111.87  5337.1 1116.82  5379.2 1119.53  5430.3 1131.65  5471.3 1135.33
#Mann=5,-1,0
  4006.2    0.12       0  5027.1    0.07       0  5056.0    0.12       0
  5215.1    0.05       0  5337.1    0.12       0
Bank Sta=5027.1,5056
Exp/Cntr=0.3,0.1

Type RM Length L Ch R = 1,44154,507,507,507
BEGIN DESCRIPTION:
LITTLE LLANO RIVER 81.0
END DESCRIPTION:
XS GIS Cut Line= 3
      2839655.71     10285403.12      2839280.75     10285253.00
      2838905.69     10285103.11
#Sta/Elev= 30
  4596.1 1112.35  4800.1 1106.60  4909.7 1102.52  4919.3 1101.10  4928.6 1097.03
  4933.9 1095.82  4940.8 1092.04  4958.2 1087.18  4973.1 1085.48  4980.1 1082.73
  4980.6 1082.23  5009.1 1082.73  5041.6 1087.49  5059.3 1094.67  5065.9 1098.70
  5080.8 1100.94  5090.1 1103.59  5095.5 1103.59  5102.4 1105.55  5119.7 1108.19
  5167.0 1110.21  5197.9 1113.14  5227.5 1119.80  5274.7 1125.98  5296.2 1130.44
  5311.0 1132.50  5328.5 1133.19  5362.0 1136.68  5364.9 1136.45  5403.9 1141.39
#Mann=5,-1,0
  4596.1    0.05       0  4800.1    0.12       0  4980.1    0.07       0
  5009.1    0.12       0  5362.0    0.05       0
Bank Sta=4980.1,5009.1
Exp/Cntr=0.3,0.1

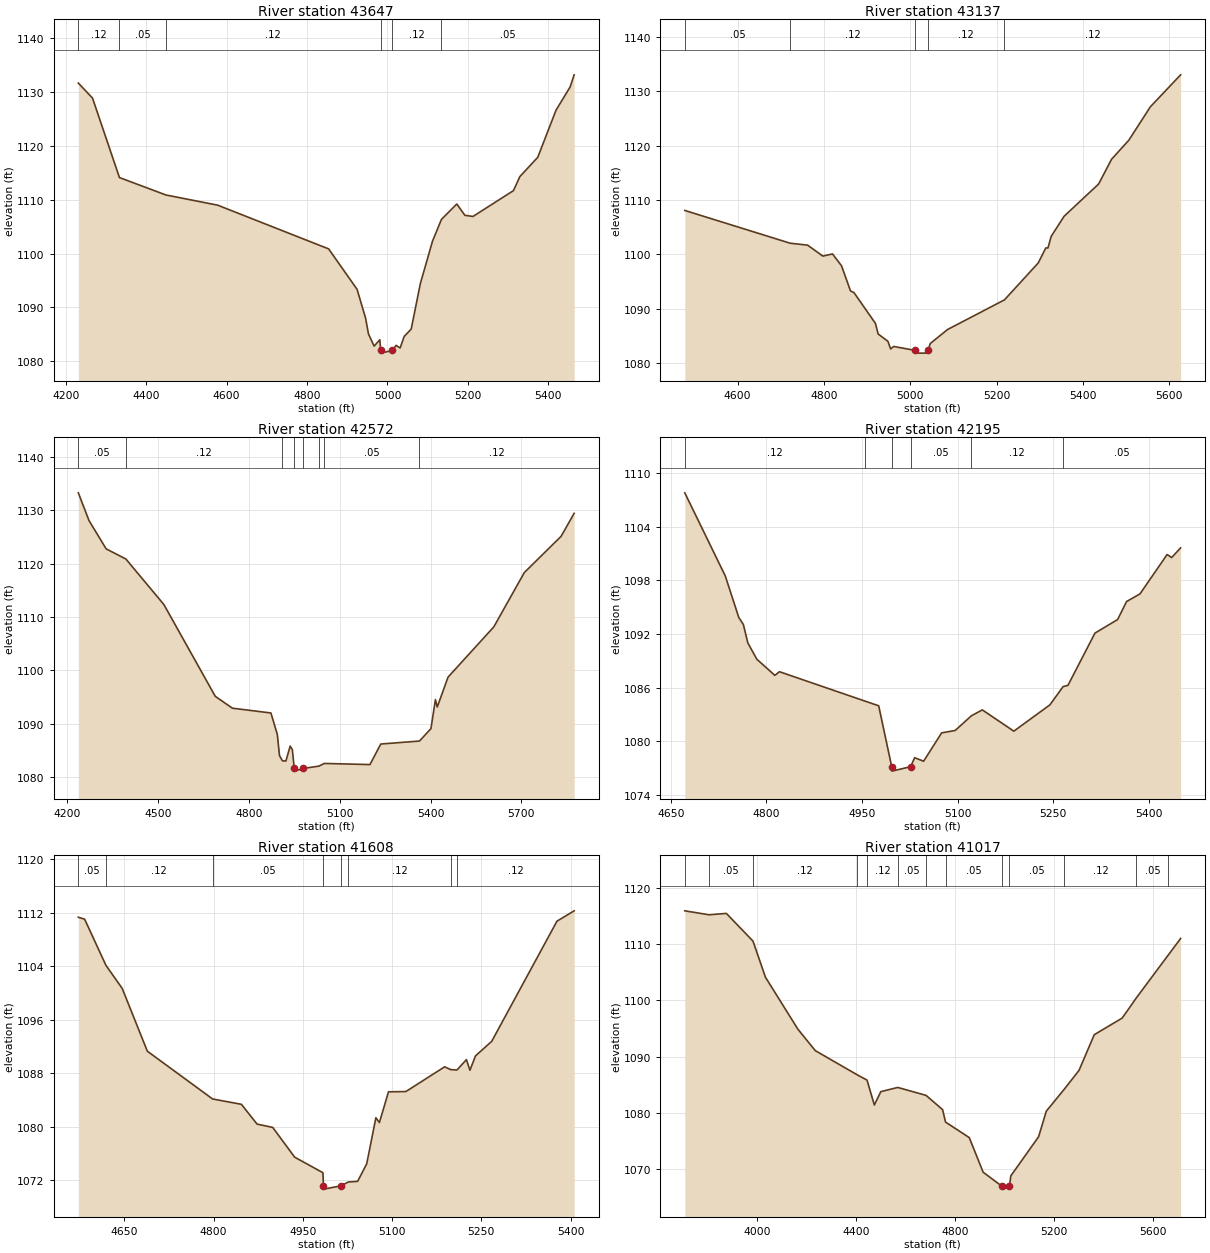
Type RM Length L Ch R = 1,43647,510,510,510
BEGIN DESCRIPTION:
LITTLE LLANO RIVER 80.0
END DESCRIPTION:
XS GIS Cut Line= 3
      2840055.68     10285353.10      2839517.00     10284805.00
      2839055.71     10284753.11
#Sta/Elev= 30
  4231.5 1131.71  4266.8 1128.91  4333.7 1114.13  4449.2 1110.89  4578.0 1108.99
  4853.8 1100.86  4924.5 1093.34  4945.7 1087.97  4952.8 1085.05  4966.9 1082.77
  4981.0 1083.96  4983.3 1081.97  4983.8 1081.47  5012.4 1081.97  5021.5 1082.92
  5031.5 1082.42  5041.6 1084.57  5059.1 1085.95  5081.8 1094.40  5112.0 1102.29
  5134.3 1106.35  5172.4 1109.21  5192.5 1107.11  5212.6 1106.89  5313.3 1111.70
  5329.2 1114.31  5373.7 1117.90  5419.2 1126.67  5454.2 1130.99  5464.2 1133.24
#Mann=6,-1,0
  4231.5    0.12       0  4333.7    0.05       0  4449.2    0.12       0
  4983.3    0.07       0  5012.4    0.12       0  5134.3    0.05       0
Bank Sta=4983.3,5012.4
Exp/Cntr=0.3,0.1

Type RM Length L Ch R = 1,43137,565,565,565
BEGIN DESCRIPTION:
LITTLE LLANO RIVER 79.0
END DESCRIPTION:
XS GIS Cut Line= 3
      2840055.68     10284753.11      2839732.25     10284343.00
      2839105.73     10284353.11
#Sta/Elev= 30
  4477.7 1108.09  4722.1 1102.05  4762.3 1101.70  4797.5 1099.68  4820.0 1100.08
  4840.9 1097.89  4861.7 1093.26  4869.7 1092.96  4919.4 1087.29  4925.8 1085.33
  4948.3 1083.99  4954.7 1082.58  4961.7 1083.04  5011.9 1082.31  5012.4 1081.81
  5040.8 1081.81  5041.3 1082.31  5046.6 1083.59  5086.6 1086.16  5218.4 1091.62
  5296.6 1098.41  5314.2 1101.18  5319.2 1101.18  5326.6 1103.30  5356.6 1107.02
  5436.6 1112.96  5466.6 1117.52  5506.6 1121.03  5556.6 1127.19  5626.6 1133.07
#Mann=5,-1,0
  4477.7    0.05       0  4722.1    0.12       0  5011.9    0.07       0
  5041.3    0.12       0  5218.4    0.12       0
Bank Sta=5011.9,5041.3
Exp/Cntr=0.3,0.1

Type RM Length L Ch R = 1,42572,377,377,377
BEGIN DESCRIPTION:
LITTLE LLANO RIVER 78.0
END DESCRIPTION:
XS GIS Cut Line= 3
      2840405.68     10283253.12      2839867.25     10283795.00
      2839155.65     10284303.14
#Sta/Elev= 30
  4236.1 1133.26  4271.4 1128.06  4328.0 1122.76  4393.3 1120.85  4518.9 1112.31
  4688.6 1095.11  4745.2 1092.89  4872.5 1091.99  4893.7 1087.95  4900.8 1083.99
  4910.6 1083.02  4922.0 1082.99  4936.1 1085.78  4943.2 1085.13  4949.6 1081.59
  4950.1 1081.09  4979.3 1081.59  5031.1 1082.03  5048.8 1082.53  5199.7 1082.32
  5235.4 1086.17  5363.3 1086.73  5401.2 1089.06  5416.0 1094.50  5422.1 1093.11
  5457.7 1098.71  5608.9 1108.13  5709.7 1118.31  5831.3 1125.11  5874.4 1129.42
#Mann=8,-1,0
  4236.1    0.05       0  4393.3    0.12       0  4910.6    0.05       0
  4949.6    0.03       0  4979.3    0.05       0  5031.1    0.12       0
  5048.8    0.05       0  5363.3    0.12       0
Bank Sta=4949.6,4979.3
Exp/Cntr=0.3,0.1

Type RM Length L Ch R = 1,42195,587,587,587
BEGIN DESCRIPTION:
LITTLE LLANO RIVER 77.0
END DESCRIPTION:
XS GIS Cut Line= 3
      2839955.67     10283253.13      2839727.75     10283489.00
      2839405.67     10283803.13
#Sta/Elev= 30
  4672.0 1107.79  4735.6 1098.48  4756.7 1093.85  4763.9 1093.06  4770.9 1091.00
  4785.0 1089.18  4813.3 1087.37  4820.5 1087.78  4955.2 1084.48  4976.2 1083.97
  4996.6 1077.16  4997.1 1076.66  5026.3 1077.16  5032.6 1078.16  5046.7 1077.77
  5075.0 1080.94  5096.3 1081.21  5121.6 1082.85  5138.8 1083.51  5188.2 1081.13
  5244.8 1084.07  5265.6 1086.12  5273.1 1086.25  5315.5 1092.10  5351.0 1093.61
  5365.1 1095.63  5386.2 1096.49  5428.7 1100.89  5435.8 1100.55  5449.9 1101.63
#Mann=6,-1,0
  4672.0    0.12       0  4955.2    0.05       0  4996.6    0.05       0
  5026.3    0.05       0  5121.6    0.12       0  5265.6    0.05       0
Bank Sta=4996.6,5026.3
Exp/Cntr=0.3,0.1

Type RM Length L Ch R = 1,41608,591,591,591
BEGIN DESCRIPTION:
LITTLE LLANO RIVER 76.0
END DESCRIPTION:
XS GIS Cut Line= 3
      2840005.73     10283103.13      2839600.25     10282968.00
      2839255.67     10282753.10
#Sta/Elev= 30
  4572.6 1111.34  4583.2 1111.05  4619.0 1104.15  4646.4 1100.68  4688.6 1091.30
  4798.3 1084.15  4846.7 1083.35  4873.1 1080.39  4899.4 1079.89  4936.3 1075.44
  4983.7 1073.12  4984.7 1071.16  4985.2 1070.66  5014.5 1071.16  5026.4 1071.73
  5042.1 1071.82  5057.4 1074.45  5072.8 1081.34  5078.7 1080.62  5094.0 1085.22
  5123.2 1085.26  5188.4 1088.96  5198.6 1088.54  5209.2 1088.49  5225.0 1090.04
  5230.9 1088.45  5240.3 1090.60  5267.5 1092.77  5377.2 1110.75  5406.1 1112.30
#Mann=8,-1,0
  4572.6    0.05       0  4619.0    0.12       0  4798.3    0.05       0
  4984.7    0.05       0  5014.5    0.05       0  5026.4    0.12       0
  5198.6    0.05       0  5209.2    0.12       0
Bank Sta=4984.7,5014.5
Exp/Cntr=0.3,0.1

Type RM Length L Ch R = 1,41017,511,511,511
BEGIN DESCRIPTION:
Mapping XS b80c3cfd
END DESCRIPTION:
XS GIS Cut Line= 4
      2841208.49     10282826.59      2840514.08     10282652.99
      2839646.02     10282479.38      2839255.38     10282566.19
#Sta/Elev= 30
  3708.7 1115.95  3806.3 1115.25  3876.5 1115.49  3984.0 1110.56  4034.3 1104.13
  4165.1 1094.90  4235.3 1091.08  4405.7 1086.75  4444.1 1085.84  4473.8 1081.41
  4499.8 1083.78  4568.3 1084.53  4682.4 1083.12  4749.2 1080.58  4761.1 1078.37
  4856.8 1075.61  4912.9 1069.45  4989.2 1066.94  4989.7 1066.44  5019.1 1066.94
  5024.5 1068.79  5136.7 1075.76  5167.8 1080.31  5241.1 1084.26  5299.9 1087.57
  5361.3 1093.91  5474.0 1096.87  5531.3 1100.47  5660.1 1108.09  5709.9 1111.03
#Mann=13,-1,0
  3708.7    0.12       0  3806.3    0.05       0  3984.0    0.12       0
  4405.7    0.05       0  4444.1    0.12       0  4568.3    0.05       0
  4682.4    0.12       0  4761.1    0.05       0  4989.2    0.03       0
  5019.1    0.05       0  5241.1    0.12       0  5531.3    0.05       0
  5660.1    0.12       0
Bank Sta=4989.2,5019.1
Exp/Cntr=0.3,0.1