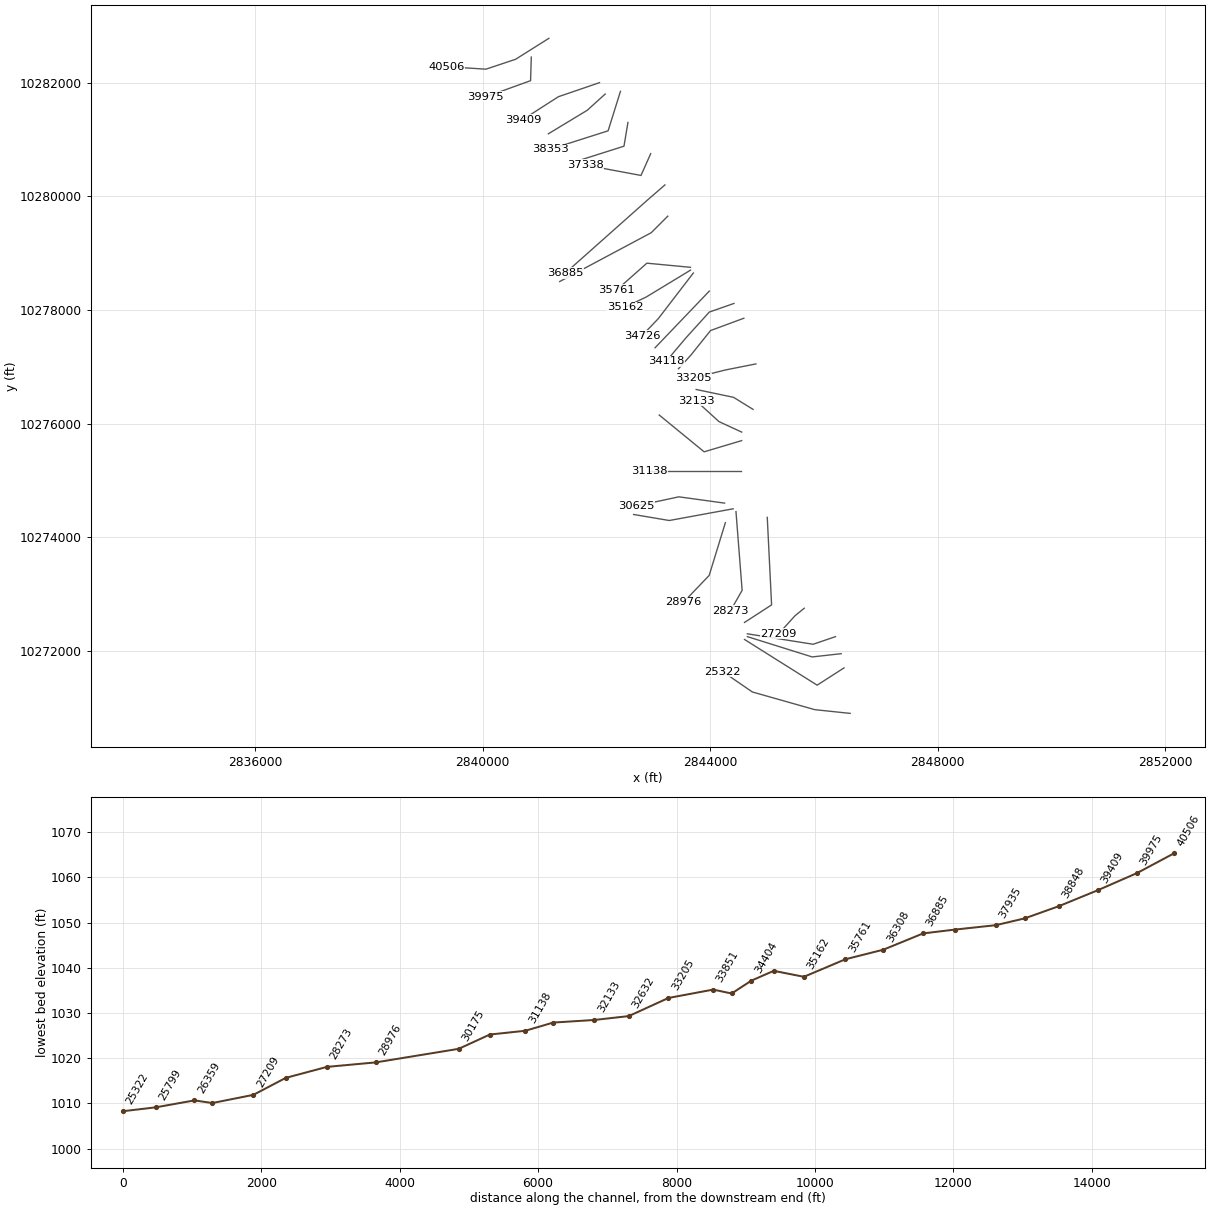
HEC-RAS study LITTLE LLANO RIVER.prj: LITTLE LLANO RIVER Base Level Engineering

--- LITTLE LLANO RIVER.g01 (geometry) --- (continued)

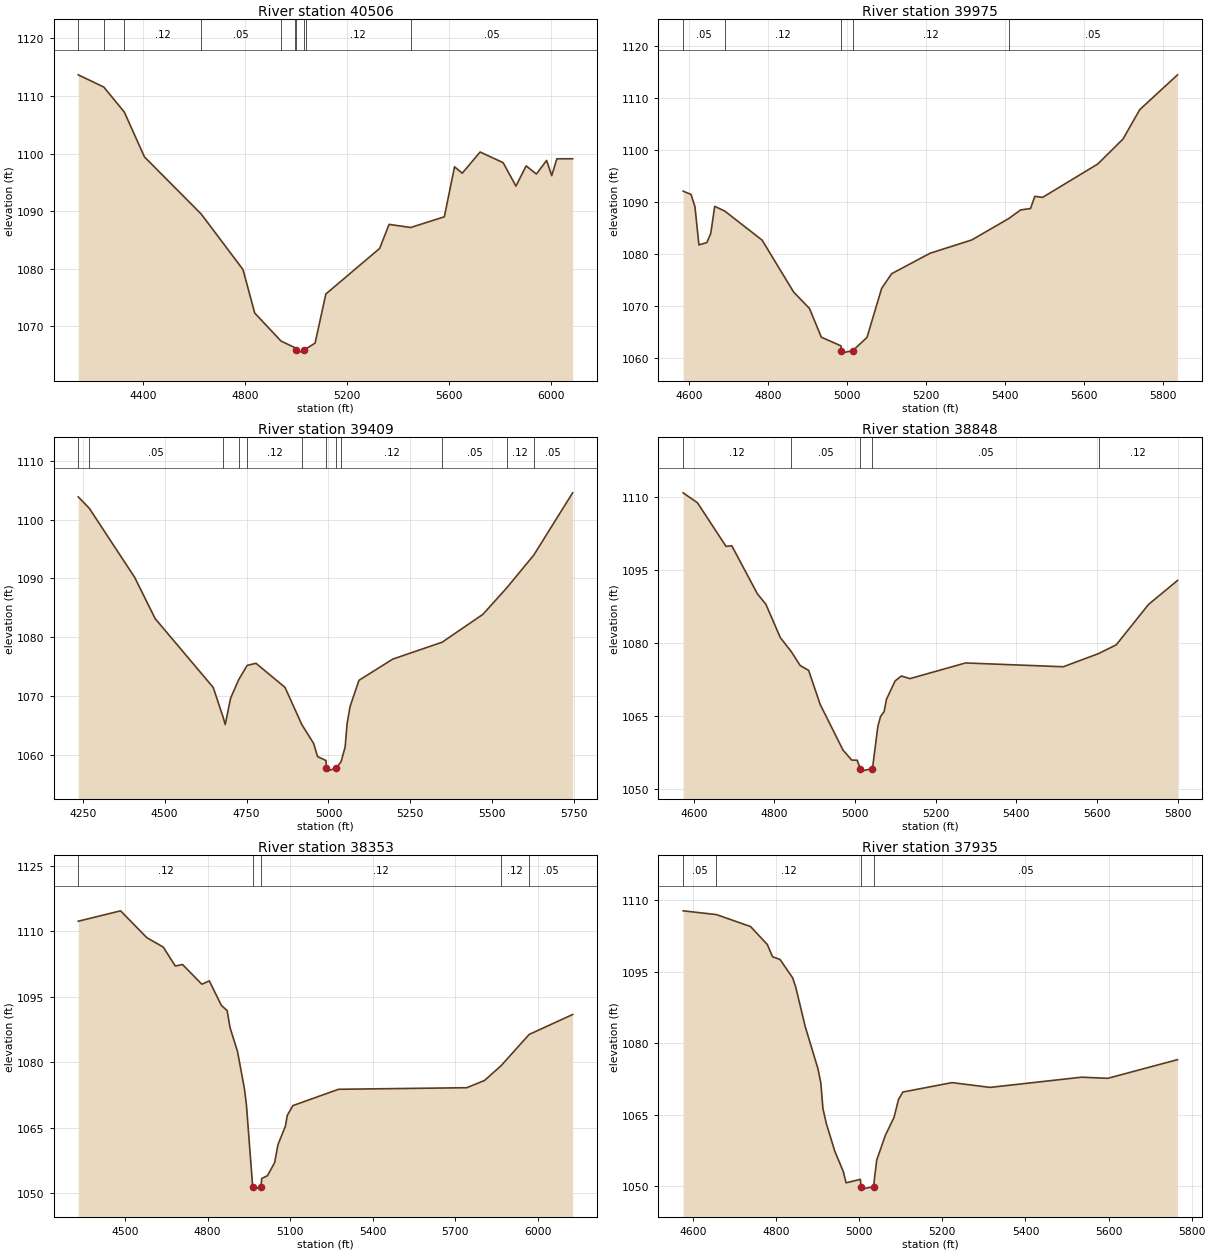
Type RM Length L Ch R = 1,40506,531,531,531
BEGIN DESCRIPTION:
Mapping XS cc0999e5
END DESCRIPTION:
XS GIS Cut Line= 4
      2841165.12     10282783.19      2840579.18     10282414.27
      2840058.35     10282240.66      2839363.91     10282284.06
#Sta/Elev= 30
  4147.4 1113.68  4247.4 1111.56  4328.0 1107.20  4406.8 1099.41  4629.6 1089.46
  4792.9 1079.83  4838.9 1072.27  4941.9 1067.40  4996.0 1066.26  5002.5 1065.80
  5003.0 1065.30  5032.4 1065.80  5039.6 1066.05  5075.4 1067.04  5117.6 1075.58
  5328.4 1083.50  5365.3 1087.68  5450.1 1087.14  5581.8 1089.00  5621.9 1097.69
  5652.0 1096.58  5722.1 1100.26  5812.3 1098.41  5862.4 1094.34  5902.5 1097.85
  5942.6 1096.43  5982.6 1098.80  6002.7 1096.15  6022.7 1099.08  6084.6 1099.09
#Mann=10,-1,0
  4147.4    0.12       0  4247.4    0.05       0  4328.0    0.12       0
  4629.6    0.05       0  4941.9    0.12       0  4996.0    0.05       0
  5002.5    0.05       0  5032.4    0.05       0  5039.6    0.12       0
  5450.1    0.05       0
Bank Sta=5002.5,5032.4
Exp/Cntr=0.3,0.1

Type RM Length L Ch R = 1,39975,566,566,566
BEGIN DESCRIPTION:
LITTLE LLANO RIVER 73.0
END DESCRIPTION:
XS GIS Cut Line= 3
      2840855.68     10282453.11      2840843.25     10282038.00
      2840055.69     10281753.11
#Sta/Elev= 30
  4584.7 1092.13  4604.7 1091.51  4614.7 1089.14  4624.7 1081.79  4644.7 1082.23
  4654.7 1083.99  4664.7 1089.21  4690.2 1088.30  4784.8 1082.71  4864.8 1072.71
  4904.8 1069.56  4934.9 1064.03  4984.9 1062.35  4985.0 1061.46  4985.5 1060.96
  5014.9 1061.46  5050.6 1063.98  5087.8 1073.43  5113.2 1076.25  5210.4 1080.18
  5316.4 1082.75  5410.4 1086.89  5439.7 1088.51  5465.0 1088.79  5475.9 1091.13
  5495.7 1090.94  5635.5 1097.36  5699.3 1102.16  5741.8 1107.82  5837.5 1114.52
#Mann=5,-1,0
  4584.7    0.05       0  4690.2    0.12       0  4985.0    0.07       0
  5014.9    0.12       0  5410.4    0.05       0
Bank Sta=4985,5014.9
Exp/Cntr=0.3,0.1

Type RM Length L Ch R = 1,39409,561,561,561
BEGIN DESCRIPTION:
LITTLE LLANO RIVER 72.0
END DESCRIPTION:
XS GIS Cut Line= 3
      2842055.72     10282003.12      2841333.00     10281756.00
      2840705.73     10281353.14
#Sta/Elev= 30
  4236.2 1103.86  4270.0 1101.91  4408.4 1090.16  4471.0 1083.13  4648.3 1071.41
  4677.9 1066.46  4684.9 1065.10  4701.2 1069.58  4726.2 1072.76  4751.8 1075.17
  4778.8 1075.53  4867.5 1071.42  4918.6 1065.11  4954.9 1061.87  4966.7 1059.65
  4992.7 1058.97  4993.7 1057.67  4994.2 1057.17  5023.7 1057.67  5038.7 1058.80
  5050.9 1061.26  5056.9 1065.25  5066.1 1068.18  5093.2 1072.63  5196.3 1076.24
  5347.2 1079.12  5471.7 1083.87  5543.9 1088.34  5627.0 1093.96  5745.5 1104.55
#Mann=12,-1,0
  4236.2    0.12       0  4270.0    0.05       0  4677.9    0.12       0
  4726.2    0.05       0  4751.8    0.12       0  4918.6    0.05       0
  4993.7    0.05       0  5023.7    0.05       0  5038.7    0.12       0
  5347.2    0.05       0  5543.9    0.12       0  5627.0    0.05       0
Bank Sta=4993.7,5023.7
Exp/Cntr=0.3,0.1

Type RM Length L Ch R = 1,38848,495,495,495
BEGIN DESCRIPTION:
LITTLE LLANO RIVER 71.0
END DESCRIPTION:
XS GIS Cut Line= 3
      2842155.66     10281803.09      2841839.75     10281517.00
      2841155.71     10281103.13
#Sta/Elev= 30
  4573.8 1110.87  4609.3 1108.83  4680.2 1099.86  4694.4 1099.99  4757.9 1090.11
  4778.9 1087.97  4814.7 1081.12  4842.2 1078.19  4864.0 1075.36  4885.0 1074.36
  4913.4 1067.40  4970.2 1057.98  4991.8 1055.92  5005.3 1055.89  5013.1 1054.15
  5013.6 1053.65  5043.2 1054.15  5056.6 1062.87  5063.2 1064.88  5072.1 1065.88
  5077.9 1068.42  5099.3 1072.19  5114.8 1073.21  5136.1 1072.67  5273.9 1075.89
  5516.3 1075.11  5603.6 1077.81  5647.6 1079.62  5727.7 1087.93  5799.5 1092.85
#Mann=5,-1,0
  4573.8    0.12       0  4842.2    0.05       0  5013.1    0.05       0
  5043.2    0.05       0  5603.6    0.12       0
Bank Sta=5013.1,5043.2
Exp/Cntr=0.3,0.1

Type RM Length L Ch R = 1,38353,418,418,418
BEGIN DESCRIPTION:
Mapping XS 00b06fb3
END DESCRIPTION:
XS GIS Cut Line= 3
      2842423.82     10281850.08      2842206.79     10281155.59
      2841186.79     10280830.06
#Sta/Elev= 30
  4329.3 1112.28  4483.3 1114.66  4578.6 1108.52  4638.4 1106.36  4682.3 1102.02
  4708.6 1102.37  4778.8 1097.86  4806.0 1098.62  4850.0 1093.00  4870.9 1091.82
  4881.4 1087.93  4908.7 1082.42  4933.8 1073.90  4941.1 1070.19  4963.8 1051.44
  4964.3 1050.94  4993.9 1051.44  4996.6 1053.38  5017.6 1054.01  5043.8 1057.04
  5055.6 1061.10  5082.9 1065.37  5089.6 1067.82  5109.9 1070.06  5276.1 1073.80
  5742.5 1074.16  5806.9 1075.81  5867.2 1079.19  5969.5 1086.36  6127.6 1090.92
#Mann=5,-1,0
  4329.3    0.12       0  4963.8    0.05       0  4993.9    0.12       0
  5867.2    0.12       0  5969.5    0.05       0
Bank Sta=4963.8,4993.9
Exp/Cntr=0.3,0.1

Type RM Length L Ch R = 1,37935,597,597,597
BEGIN DESCRIPTION:
LITTLE LLANO RIVER 69.0
END DESCRIPTION:
XS GIS Cut Line= 3
      2842555.68     10281303.09      2842485.75     10280885.00
      2841755.69     10280653.11
#Sta/Elev= 30
  4576.1 1107.78  4656.3 1106.99  4738.3 1104.49  4778.9 1100.70  4791.2 1098.16
  4809.3 1097.58  4839.7 1093.73  4846.8 1091.89  4870.1 1083.46  4900.5 1074.72
  4907.5 1071.68  4912.6 1066.31  4920.8 1063.17  4941.1 1057.38  4961.4 1053.17
  4968.3 1050.75  5002.7 1051.48  5004.2 1049.93  5004.7 1049.43  5034.3 1049.93
  5042.0 1055.52  5063.0 1060.75  5083.8 1064.50  5094.5 1068.24  5105.0 1069.79
  5223.3 1071.76  5314.8 1070.76  5535.2 1072.90  5598.1 1072.66  5766.0 1076.58
#Mann=4,-1,0
  4576.1    0.05       0  4656.3    0.12       0  5004.2    0.07       0
  5034.3    0.05       0
Bank Sta=5004.2,5034.3
Exp/Cntr=0.3,0.1

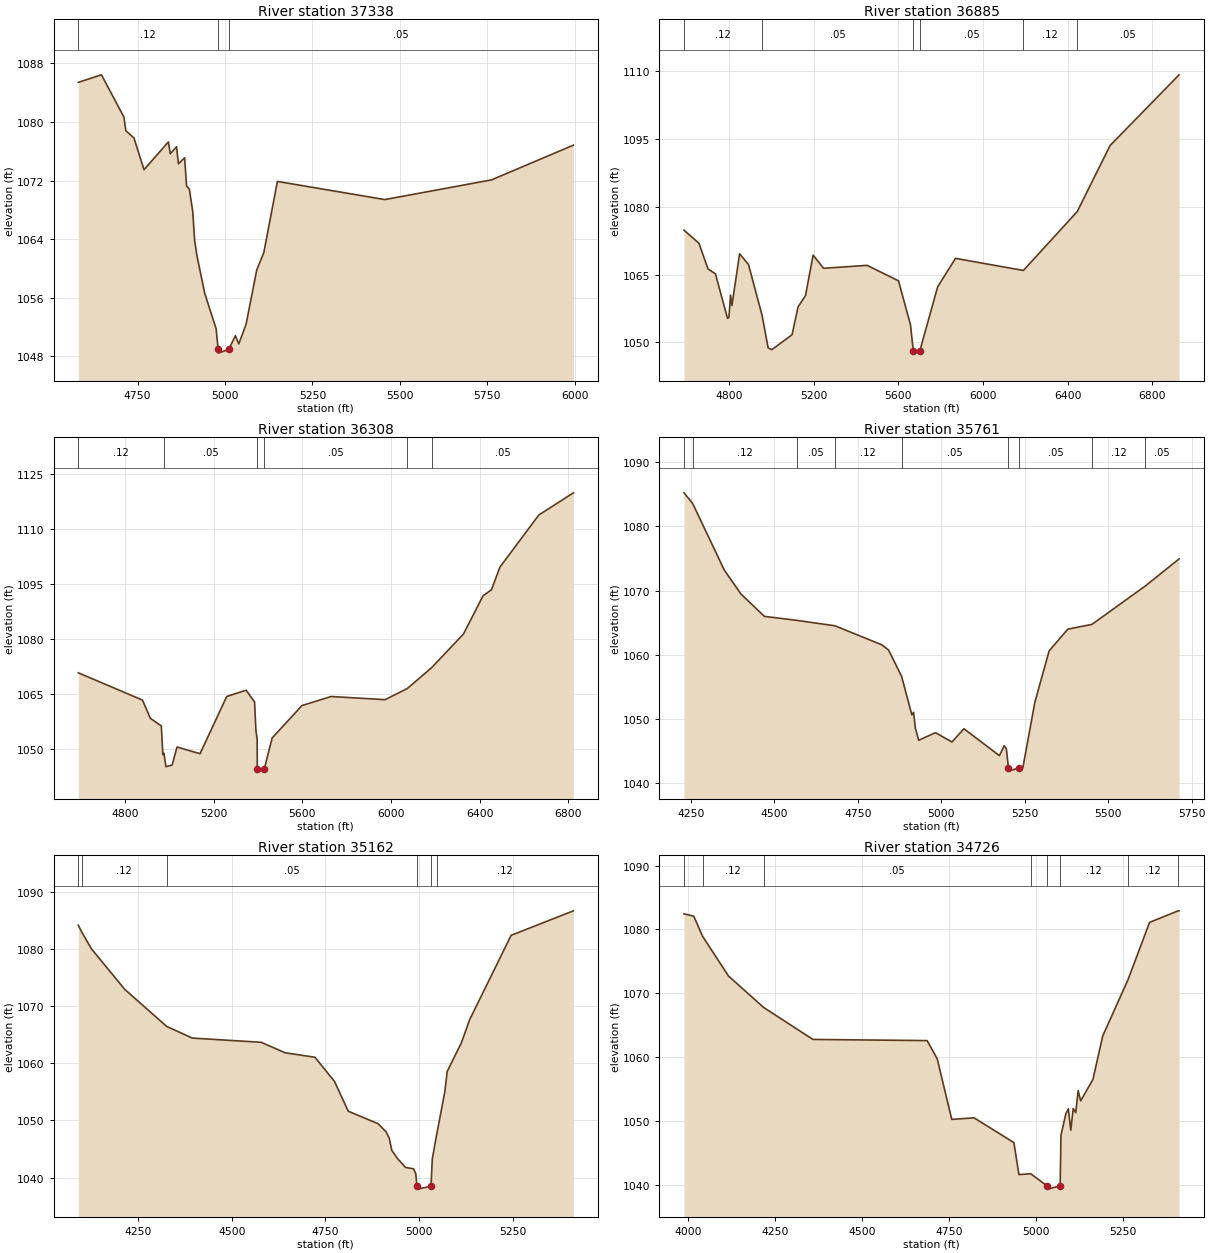
Type RM Length L Ch R = 1,37338,453,453,453
BEGIN DESCRIPTION:
LITTLE LLANO RIVER 68.0
END DESCRIPTION:
XS GIS Cut Line= 3
      2842955.68     10280753.10      2842785.00     10280370.00
      2841805.67     10280553.11
#Sta/Elev= 30
  4580.6 1085.40  4646.9 1086.43  4711.1 1080.65  4716.6 1078.80  4739.8 1077.81
  4768.5 1073.48  4838.2 1077.27  4843.7 1075.66  4861.5 1076.61  4866.9 1074.28
  4884.7 1075.10  4890.2 1071.24  4898.1 1070.84  4907.9 1067.75  4913.4 1063.77
  4920.0 1061.71  4942.1 1056.60  4974.7 1051.77  4980.5 1048.94  4981.0 1048.44
  5010.7 1048.94  5029.8 1050.82  5039.5 1049.70  5060.3 1052.37  5090.9 1059.80
  5111.2 1062.19  5149.9 1071.88  5457.1 1069.40  5762.3 1072.09  5996.3 1076.83
#Mann=3,-1,0
  4580.6    0.12       0  4980.5    0.05       0  5010.7    0.05       0
Bank Sta=4980.5,5010.7
Exp/Cntr=0.3,0.1

Type RM Length L Ch R = 1,36885,577,577,577
BEGIN DESCRIPTION:
LITTLE LLANO RIVER 67.0
END DESCRIPTION:
XS GIS Cut Line= 3
      2843205.71     10280203.14      2842894.50     10279933.00
      2841455.68     10278653.11
#Sta/Elev= 30
  4587.9 1074.84  4658.7 1071.93  4701.4 1066.25  4736.5 1065.16  4793.5 1055.30
  4800.2 1055.51  4807.8 1060.44  4814.4 1058.16  4850.5 1069.60  4892.5 1067.24
  4956.7 1055.98  4985.2 1048.79  5002.6 1048.37  5098.2 1051.68  5126.6 1057.85
  5161.8 1060.36  5197.7 1069.31  5247.1 1066.39  5452.8 1067.04  5600.8 1063.62
  5657.6 1053.86  5670.6 1048.11  5671.1 1047.61  5701.6 1048.11  5785.6 1062.27
  5870.0 1068.59  6190.6 1065.91  6445.2 1078.97  6600.0 1093.58  6925.7 1109.22
#Mann=6,-1,0
  4587.9    0.12       0  4956.7    0.05       0  5670.6    0.05       0
  5701.6    0.05       0  6190.6    0.12       0  6445.2    0.05       0
Bank Sta=5670.6,5701.6
Exp/Cntr=0.3,0.1

Type RM Length L Ch R = 1,36308,547,547,547
BEGIN DESCRIPTION:
LITTLE LLANO RIVER 66.0
END DESCRIPTION:
XS GIS Cut Line= 3
      2843255.71     10279653.13      2842964.75     10279362.00
      2841355.73     10278503.13
#Sta/Elev= 30
  4588.4 1070.77  4878.3 1063.33  4913.7 1058.38  4963.2 1056.30  4970.3 1048.48
  4974.9 1048.85  4984.4 1045.21  5012.1 1045.66  5034.1 1050.56  5138.2 1048.74
  5258.5 1064.32  5346.4 1066.03  5384.3 1062.79  5390.3 1055.22  5395.9 1052.66
  5396.7 1044.50  5397.2 1044.00  5427.7 1044.50  5463.7 1053.03  5598.5 1061.85
  5730.2 1064.31  5973.8 1063.45  6074.0 1066.49  6183.5 1072.14  6327.9 1081.35
  6415.9 1091.73  6453.9 1093.35  6492.2 1099.54  6667.8 1113.72  6823.9 1119.75
#Mann=6,-1,0
  4588.4    0.12       0  4974.9    0.05       0  5396.7    0.05       0
  5427.7    0.05       0  6074.0    0.12       0  6183.5    0.05       0
Bank Sta=5396.7,5427.7
Exp/Cntr=0.3,0.1

Type RM Length L Ch R = 1,35761,599,599,599
BEGIN DESCRIPTION:
LITTLE LLANO RIVER 65.0
END DESCRIPTION:
XS GIS Cut Line= 3
      2843655.65     10278753.12      2842888.50     10278826.00
      2842355.69     10278353.11
#Sta/Elev= 30
  4229.4 1085.23  4255.0 1083.62  4349.9 1073.23  4400.1 1069.47  4470.4 1065.99
  4567.4 1065.37  4681.9 1064.52  4822.0 1061.56  4842.1 1060.76  4881.1 1056.67
  4912.0 1050.65  4917.0 1051.04  4922.5 1048.58  4932.5 1046.70  4982.7 1047.88
  5032.1 1046.43  5068.0 1048.49  5174.2 1044.30  5188.5 1045.85  5195.1 1045.33
  5201.4 1042.39  5201.9 1041.89  5232.5 1042.39  5244.5 1042.43  5280.5 1052.63
  5323.1 1060.61  5379.1 1064.00  5451.3 1064.74  5611.5 1070.73  5712.4 1074.94
#Mann=9,-1,0
  4229.4    0.05       0  4255.0    0.12       0  4567.4    0.05       0
  4681.9    0.12       0  4881.1    0.05       0  5201.4    0.05       0
  5232.5    0.05       0  5451.3    0.12       0  5611.5    0.05       0
Bank Sta=5201.4,5232.5
Exp/Cntr=0.3,0.1

Type RM Length L Ch R = 1,35162,436,436,436
BEGIN DESCRIPTION:
LITTLE LLANO RIVER 64.0
END DESCRIPTION:
XS GIS Cut Line= 3
      2843655.70     10278703.12      2842877.75     10278231.00
      2842505.69     10278053.11
#Sta/Elev= 30
  4090.0 1084.11  4099.9 1082.85  4125.1 1079.99  4214.1 1072.91  4326.0 1066.44
  4394.4 1064.40  4578.5 1063.66  4642.5 1061.83  4722.0 1061.05  4774.3 1056.83
  4811.1 1051.62  4890.6 1049.45  4911.9 1048.04  4920.5 1046.92  4927.4 1044.77
  4942.9 1043.34  4964.2 1041.80  4985.6 1041.56  4991.4 1040.72  4994.6 1038.51
  4995.6 1038.01  5032.1 1038.51  5035.5 1043.27  5047.0 1047.47  5068.8 1054.96
  5075.3 1058.57  5113.1 1063.56  5135.3 1067.61  5246.1 1082.35  5412.4 1086.63
#Mann=6,-1,0
  4090.0    0.05       0  4099.9    0.12       0  4326.0    0.05       0
  4994.6    0.05       0  5032.1    0.05       0  5047.0    0.12       0
Bank Sta=4994.6,5032.1
Exp/Cntr=0.3,0.1

Type RM Length L Ch R = 1,34726,322,322,322
BEGIN DESCRIPTION:
LITTLE LLANO RIVER 63.0
END DESCRIPTION:
XS GIS Cut Line= 3
      2843705.68     10278653.11      2843089.75     10277850.00
      2842805.68     10277553.11
#Sta/Elev= 30
  3987.9 1082.44  4016.0 1082.08  4041.2 1078.94  4115.7 1072.71  4216.6 1067.79
  4358.6 1062.77  4686.8 1062.59  4715.8 1059.73  4757.5 1050.25  4821.8 1050.49
  4936.1 1046.62  4950.6 1041.61  4984.6 1041.73  5031.6 1039.83  5032.5 1039.33
  5069.1 1039.83  5071.4 1047.76  5085.5 1051.15  5092.6 1051.91  5099.7 1048.56
  5106.6 1051.96  5113.9 1051.30  5120.8 1054.77  5128.0 1053.15  5163.2 1056.49
  5191.5 1063.32  5263.9 1072.10  5326.1 1081.10  5408.2 1082.91  5410.9 1082.91
#Mann=8,-1,0
  3987.9    0.05       0  4041.2    0.12       0  4216.6    0.05       0
  4984.6    0.12       0  5031.6    0.07       0  5069.1    0.12       0
  5263.9    0.12       0  5408.2    0.05       0
Bank Sta=5031.6,5069.1
Exp/Cntr=0.3,0.1

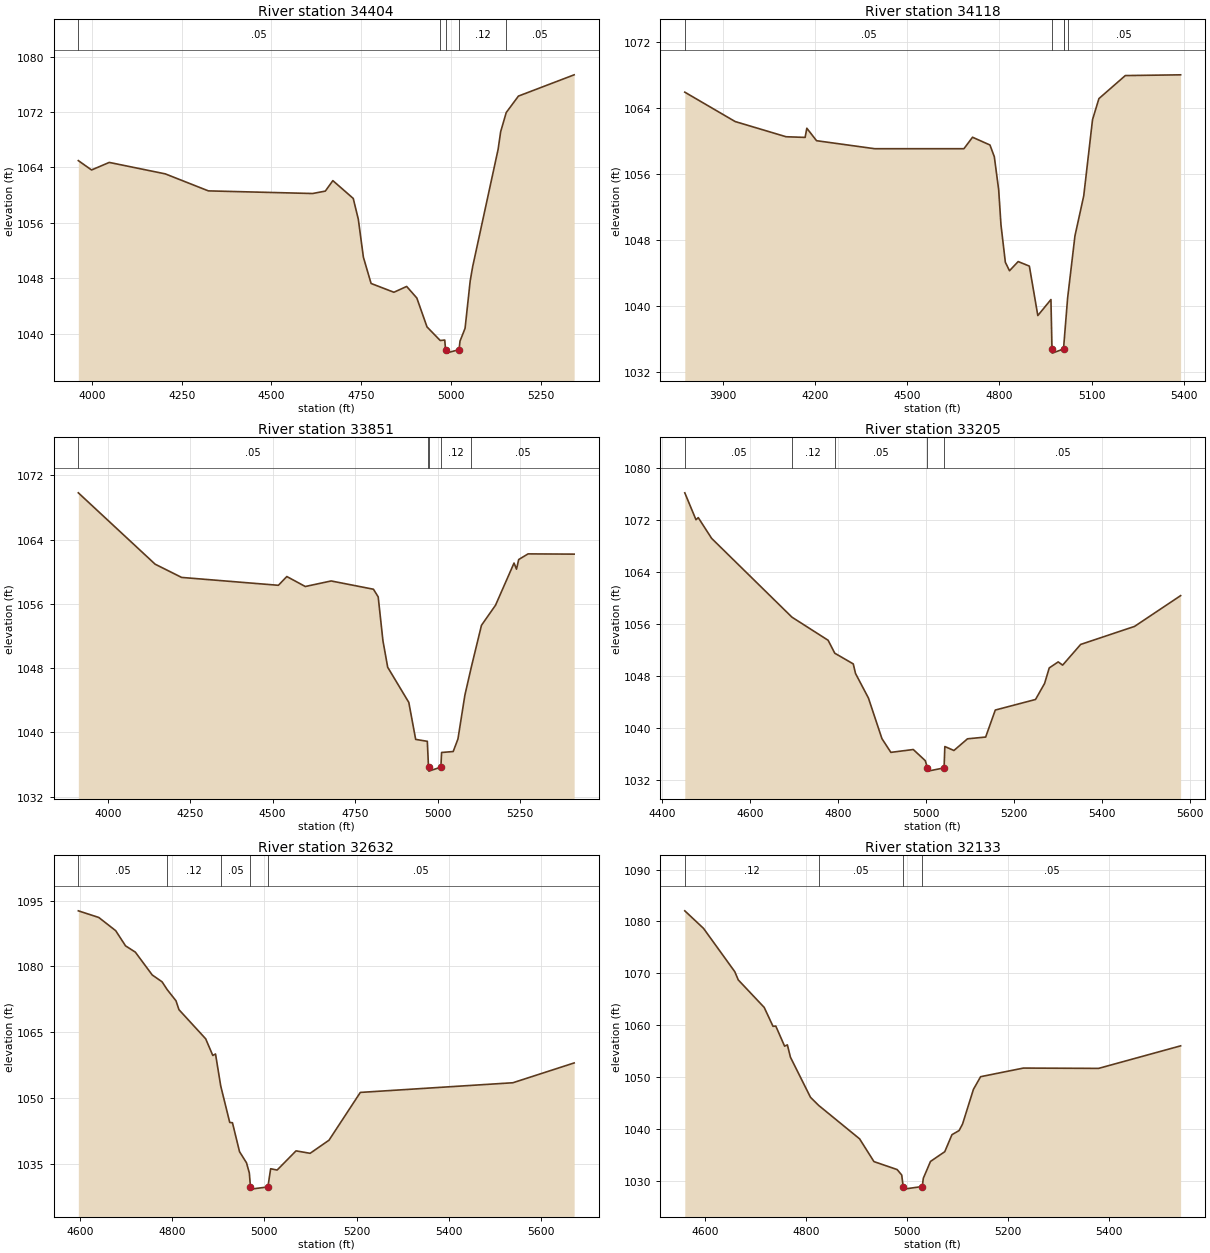
Type RM Length L Ch R = 1,34404,286,286,286
BEGIN DESCRIPTION:
Mapping XS 4596b7bb
END DESCRIPTION:
XS GIS Cut Line= 2
      2843986.33     10278334.44      2843032.38     10277337.12
#Sta/Elev= 30
  3962.4 1064.97  3999.2 1063.62  4048.5 1064.71  4204.2 1063.06  4324.4 1060.60
  4614.6 1060.22  4649.9 1060.57  4670.9 1062.08  4727.6 1059.51  4741.7 1056.51
  4755.9 1051.01  4777.3 1047.23  4840.8 1045.96  4876.3 1046.80  4904.6 1045.13
  4932.9 1040.96  4969.7 1038.99  4982.3 1039.06  4984.6 1037.67  4985.6 1037.17
  5022.1 1037.67  5024.8 1038.90  5038.9 1040.76  5053.1 1047.59  5060.0 1049.66
  5130.8 1066.59  5138.0 1069.16  5153.5 1071.92  5187.4 1074.29  5342.5 1077.36
#Mann=5,-1,0
  3962.4    0.05       0  4969.7    0.12       0  4984.6    0.07       0
  5022.1    0.12       0  5153.5    0.05       0
Bank Sta=4984.6,5022.1
Exp/Cntr=0.3,0.1

Type RM Length L Ch R = 1,34118,267,267,267
BEGIN DESCRIPTION:
Mapping XS 75f2ed68
END DESCRIPTION:
XS GIS Cut Line= 4
      2844420.36     10278117.41      2843986.30     10277965.49
      2843573.98     10277509.76      2843227.01     10277097.74
#Sta/Elev= 30
  3776.4 1065.93  3940.3 1062.37  4105.9 1060.53  4167.9 1060.45  4173.4 1061.56
  4205.1 1060.05  4394.1 1059.08  4684.5 1059.08  4712.5 1060.47  4769.2 1059.53
  4783.4 1058.11  4797.6 1054.09  4805.1 1049.84  4819.3 1045.32  4832.8 1044.30
  4861.0 1045.41  4897.4 1044.86  4924.9 1038.87  4967.6 1040.81  4971.0 1034.82
  4971.9 1034.32  5008.5 1034.82  5011.4 1036.16  5021.8 1040.97  5045.7 1048.52
  5074.3 1053.37  5102.9 1062.60  5123.7 1065.15  5209.5 1067.94  5389.5 1068.03
#Mann=5,-1,0
  3776.4    0.05       0  4971.0    0.05       0  5008.5    0.05       0
  5011.4    0.12       0  5021.8    0.05       0
Bank Sta=4971,5008.5
Exp/Cntr=0.3,0.1

Type RM Length L Ch R = 1,33851,646,646,646
BEGIN DESCRIPTION:
Mapping XS aa4b3080
END DESCRIPTION:
XS GIS Cut Line= 4
      2844593.92     10277856.97      2844008.00     10277639.97
      2843660.78     10277205.94      2843444.14     10276967.63
#Sta/Elev= 30
  3911.0 1069.82  4143.7 1060.94  4224.1 1059.29  4517.3 1058.31  4542.9 1059.40
  4598.9 1058.16  4677.3 1058.85  4805.4 1057.82  4819.8 1056.87  4834.2 1051.40
  4848.6 1048.11  4912.6 1043.73  4933.4 1039.13  4968.7 1038.89  4971.0 1036.84
  4972.3 1035.68  4973.3 1035.18  5009.8 1035.68  5011.9 1037.50  5047.1 1037.62
  5061.5 1039.18  5082.5 1044.63  5101.9 1048.11  5132.8 1053.33  5175.4 1055.83
  5231.5 1061.08  5238.9 1060.32  5245.7 1061.52  5274.0 1062.22  5413.7 1062.19
#Mann=5,-1,0
  3911.0    0.05       0  4971.0    0.12       0  4972.3    0.07       0
  5009.8    0.12       0  5101.9    0.05       0
Bank Sta=4972.3,5009.8
Exp/Cntr=0.3,0.1

Type RM Length L Ch R = 1,33205,573,573,573
BEGIN DESCRIPTION:
LITTLE LLANO RIVER 60.0
END DESCRIPTION:
XS GIS Cut Line= 3
      2844805.65     10277053.11      2844267.00     10276946.00
      2843705.70     10276803.12
#Sta/Elev= 30
  4450.8 1076.21  4476.3 1072.06  4481.4 1072.39  4511.9 1069.19  4694.7 1057.05
  4777.0 1053.49  4792.1 1051.50  4834.2 1049.85  4839.3 1048.38  4868.8 1044.58
  4899.4 1038.34  4919.8 1036.22  4970.8 1036.66  4998.1 1034.94  5003.1 1033.83
  5004.1 1033.33  5040.9 1033.83  5042.6 1037.12  5063.3 1036.51  5094.2 1038.31
  5135.5 1038.58  5157.4 1042.74  5249.0 1044.37  5269.6 1046.84  5280.2 1049.23
  5300.6 1050.16  5310.7 1049.66  5351.7 1052.85  5474.4 1055.63  5579.2 1060.37
#Mann=5,-1,0
  4450.8    0.05       0  4694.7    0.12       0  4792.1    0.05       0
  5003.1    0.05       0  5040.9    0.05       0
Bank Sta=5003.1,5040.9
Exp/Cntr=0.3,0.1

Type RM Length L Ch R = 1,32632,499,499,499
BEGIN DESCRIPTION:
LITTLE LLANO RIVER 59.0
END DESCRIPTION:
XS GIS Cut Line= 3
      2844755.67     10276253.12      2844412.75     10276465.00
      2843755.71     10276603.11
#Sta/Elev= 30
  4596.9 1092.66  4641.2 1091.15  4677.9 1088.14  4699.2 1084.69  4720.4 1083.26
  4757.1 1078.06  4778.4 1076.50  4789.6 1074.71  4808.5 1072.19  4815.0 1070.16
  4872.9 1063.53  4888.3 1059.74  4894.2 1060.08  4905.5 1052.80  4925.0 1044.50
  4930.9 1044.43  4946.2 1037.85  4961.3 1035.32  4967.5 1032.99  4969.9 1029.82
  4970.9 1029.32  5007.7 1029.82  5013.7 1033.96  5027.7 1033.66  5068.7 1038.03
  5099.2 1037.47  5140.1 1040.45  5208.0 1051.33  5538.6 1053.53  5671.4 1058.04
#Mann=5,-1,0
  4596.9    0.05       0  4789.6    0.12       0  4905.5    0.05       0
  4969.9    0.03       0  5007.7    0.05       0
Bank Sta=4969.9,5007.7
Exp/Cntr=0.3,0.1

Type RM Length L Ch R = 1,32133,592,592,592
BEGIN DESCRIPTION:
LITTLE LLANO RIVER 58.0
END DESCRIPTION:
XS GIS Cut Line= 3
      2844555.68     10275853.11      2844155.75     10276038.00
      2843755.70     10276403.09
#Sta/Elev= 30
  4559.4 1082.05  4596.5 1078.67  4658.5 1070.32  4665.3 1068.75  4716.7 1063.45
  4734.1 1059.82  4739.7 1059.85  4757.1 1055.99  4762.6 1056.24  4768.7 1053.86
  4808.4 1046.14  4824.5 1044.59  4905.7 1038.14  4934.1 1033.76  4980.0 1032.23
  4989.1 1031.18  4992.0 1028.96  4993.0 1028.46  5029.8 1028.96  5031.9 1030.55
  5046.1 1033.79  5074.4 1035.67  5088.6 1038.94  5102.8 1039.74  5109.6 1040.99
  5131.2 1047.68  5145.4 1050.11  5230.2 1051.77  5379.1 1051.71  5541.6 1056.05
#Mann=4,-1,0
  4559.4    0.12       0  4824.5    0.05       0  4992.0    0.03       0
  5029.8    0.05       0
Bank Sta=4992,5029.8
Exp/Cntr=0.3,0.1

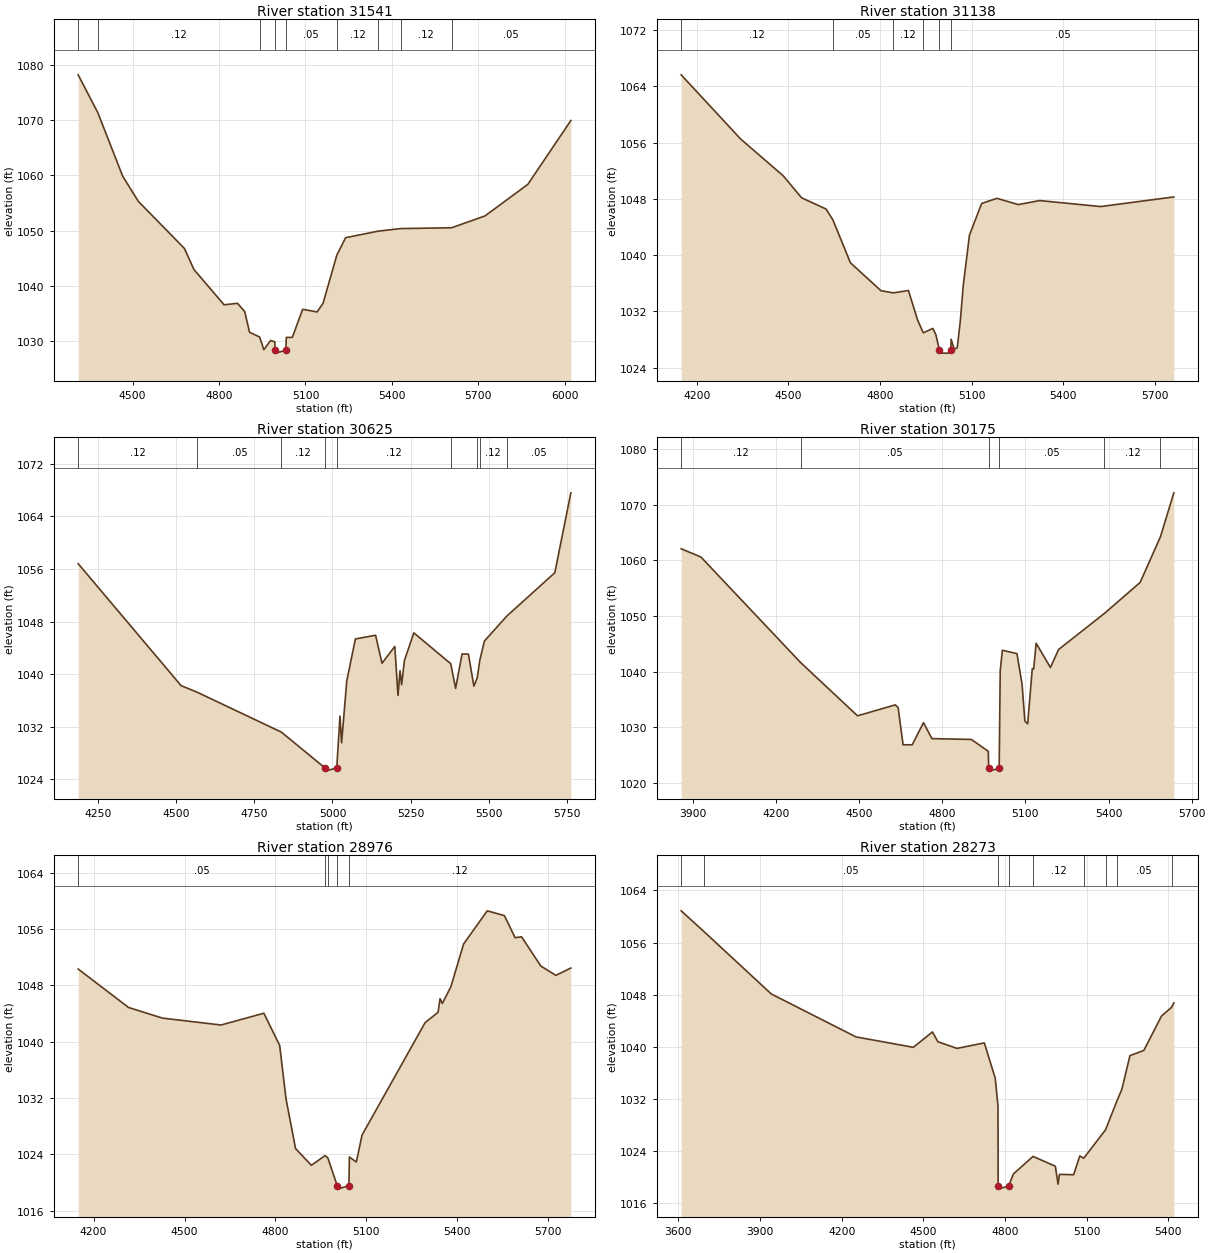
Type RM Length L Ch R = 1,31541,403,403,403
BEGIN DESCRIPTION:
LITTLE LLANO RIVER 57.0
END DESCRIPTION:
XS GIS Cut Line= 3
      2844555.70     10275703.12      2843895.50     10275506.00
      2843105.65     10276153.14
#Sta/Elev= 30
  4311.0 1078.17  4379.1 1071.35  4465.3 1059.88  4519.7 1055.32  4679.8 1046.80
  4712.9 1042.99  4817.5 1036.62  4864.1 1036.89  4889.0 1035.40  4905.9 1031.66
  4940.9 1030.80  4955.3 1028.51  4978.9 1030.17  4993.6 1029.94  4993.7 1028.39
  4994.7 1027.89  5031.6 1028.39  5033.5 1030.73  5054.3 1030.73  5090.3 1035.81
  5140.4 1035.33  5161.2 1036.92  5208.7 1045.58  5239.5 1048.75  5352.8 1049.93
  5430.0 1050.39  5607.5 1050.54  5723.2 1052.68  5871.8 1058.38  6021.1 1069.91
#Mann=9,-1,0
  4311.0    0.05       0  4379.1    0.12       0  4940.9    0.05       0
  4993.7    0.05       0  5031.6    0.05       0  5208.7    0.12       0
  5352.8    0.05       0  5430.0    0.12       0  5607.5    0.05       0
Bank Sta=4993.7,5031.6
Exp/Cntr=0.3,0.1

Type RM Length L Ch R = 1,31138,513,513,513
BEGIN DESCRIPTION:
Mapping XS e264f74b
END DESCRIPTION:
XS GIS Cut Line= 2
      2844550.49     10275159.83      2842935.89     10275159.83
#Sta/Elev= 30
  4148.5 1065.65  4343.3 1056.53  4483.3 1051.28  4543.3 1048.16  4623.3 1046.57
  4645.6 1045.04  4703.3 1038.92  4803.3 1034.96  4843.2 1034.65  4893.3 1034.98
  4923.3 1030.79  4941.9 1028.97  4973.3 1029.59  4983.3 1028.70  4994.4 1026.58
  4995.4 1026.08  5031.3 1026.08  5032.3 1026.58  5033.3 1028.05  5043.3 1026.64
  5053.3 1026.84  5063.3 1030.64  5073.3 1035.83  5093.3 1042.85  5133.3 1047.36
  5183.3 1048.09  5253.3 1047.20  5323.3 1047.77  5523.3 1046.92  5763.1 1048.29
#Mann=6,-1,0
  4148.5    0.12       0  4645.6    0.05       0  4843.2    0.12       0
  4941.9    0.05       0  4994.4    0.05       0  5032.3    0.05       0
Bank Sta=4994.4,5032.3
Exp/Cntr=0.3,0.1

Type RM Length L Ch R = 1,30625,450,450,450
BEGIN DESCRIPTION:
LITTLE LLANO RIVER 55.0
END DESCRIPTION:
XS GIS Cut Line= 3
      2844255.70     10274603.11      2843450.50     10274714.00
      2842705.68     10274553.11
#Sta/Elev= 30
  4187.2 1056.81  4516.2 1038.25  4568.4 1037.23  4836.6 1031.18  4975.8 1025.74
  4976.8 1025.24  5013.7 1025.74  5024.1 1033.61  5029.2 1029.55  5045.8 1038.97
  5073.3 1045.35  5137.9 1045.92  5158.4 1041.66  5199.3 1044.21  5209.5 1036.75
  5216.0 1040.53  5221.1 1038.39  5230.0 1042.06  5260.1 1046.28  5378.0 1041.59
  5393.7 1037.83  5414.2 1043.07  5434.6 1043.05  5452.1 1038.17  5463.0 1039.46
  5470.8 1042.07  5485.8 1045.04  5557.7 1048.85  5710.8 1055.43  5762.0 1067.59
#Mann=9,-1,0
  4187.2    0.12       0  4568.4    0.05       0  4836.6    0.12       0
  4975.8    0.05       0  5013.7    0.12       0  5378.0    0.12       0
  5463.0    0.05       0  5470.8    0.12       0  5557.7    0.05       0
Bank Sta=4975.8,5013.7
Exp/Cntr=0.3,0.1

Type RM Length L Ch R = 1,30175,1199,1199,1199
BEGIN DESCRIPTION:
LITTLE LLANO RIVER 54.0
END DESCRIPTION:
XS GIS Cut Line= 3
      2844405.65     10274503.10      2843282.50     10274297.00
      2842655.72     10274403.11
#Sta/Elev= 30
  3858.1 1062.08  3929.2 1060.61  4288.8 1041.63  4494.4 1032.03  4630.8 1034.00
  4640.9 1033.51  4658.8 1026.82  4691.8 1026.82  4732.4 1030.80  4762.9 1027.93
  4905.3 1027.78  4966.3 1025.64  4967.6 1022.58  4968.6 1022.08  5005.5 1022.58
  5009.3 1040.17  5017.1 1043.83  5069.7 1043.22  5088.1 1037.70  5098.2 1031.10
  5108.3 1030.59  5125.0 1040.53  5130.1 1040.46  5138.8 1045.09  5190.5 1040.73
  5219.9 1043.96  5385.4 1050.46  5514.0 1056.02  5587.3 1064.23  5635.7 1072.15
#Mann=6,-1,0
  3858.1    0.12       0  4288.8    0.05       0  4967.6    0.05       0
  5005.5    0.05       0  5385.4    0.12       0  5587.3    0.05       0
Bank Sta=4967.6,5005.5
Exp/Cntr=0.3,0.1

Type RM Length L Ch R = 1,28976,703,703,703
BEGIN DESCRIPTION:
Mapping XS fd9d6d5d
END DESCRIPTION:
XS GIS Cut Line= 3
      2844268.84     10274258.86      2843984.25     10273330.56
      2843531.38     10272857.41
#Sta/Elev= 30
  4149.1 1050.33  4315.3 1044.87  4427.1 1043.36  4620.5 1042.38  4762.0 1044.05
  4814.1 1039.48  4835.0 1031.91  4866.4 1024.85  4918.7 1022.46  4963.7 1023.84
  4972.9 1023.53  5003.9 1019.58  5004.9 1019.08  5042.6 1019.58  5044.2 1023.64
  5067.1 1022.93  5086.0 1026.76  5294.1 1042.72  5336.6 1044.18  5343.5 1046.12
  5350.8 1045.43  5379.1 1047.82  5421.2 1053.89  5499.2 1058.59  5555.8 1057.91
  5591.0 1054.78  5612.4 1054.90  5676.0 1050.75  5725.6 1049.43  5775.0 1050.47
#Mann=5,-1,0
  4149.1    0.05       0  4963.7     0.1       0  4972.9    0.12       0
  5003.9    0.07       0  5042.6    0.12       0
Bank Sta=5003.9,5042.6
Exp/Cntr=0.3,0.1

Type RM Length L Ch R = 1,28273,595,595,595
BEGIN DESCRIPTION:
LITTLE LLANO RIVER 50.0
END DESCRIPTION:
XS GIS Cut Line= 3
      2844455.69     10274453.09      2844563.75     10273068.00
      2844355.70     10272703.15
#Sta/Elev= 30
  3610.7 1060.87  3693.2 1057.73  3941.7 1048.09  4252.6 1041.49  4463.3 1039.89
  4533.5 1042.25  4553.5 1040.75  4623.7 1039.72  4724.1 1040.57  4764.2 1035.11
  4774.2 1030.88  4774.9 1018.59  4775.9 1018.09  4813.6 1018.59  4830.7 1020.42
  4903.0 1023.12  4984.8 1021.61  4994.9 1018.85  4999.9 1020.36  5052.0 1020.30
  5074.7 1023.19  5089.1 1022.84  5169.4 1027.22  5209.5 1031.50  5229.2 1033.45
  5258.9 1038.61  5309.8 1039.41  5374.7 1044.69  5411.5 1046.04  5420.0 1046.72
#Mann=9,-1,0
  3610.7    0.12       0  3693.2    0.05       0  4774.9    0.07       0
  4813.6    0.05       0  4903.0    0.12       0  5089.1    0.05       0
  5169.4    0.12       0  5209.5    0.05       0  5411.5    0.12       0
Bank Sta=4774.9,4813.6
Exp/Cntr=0.3,0.1

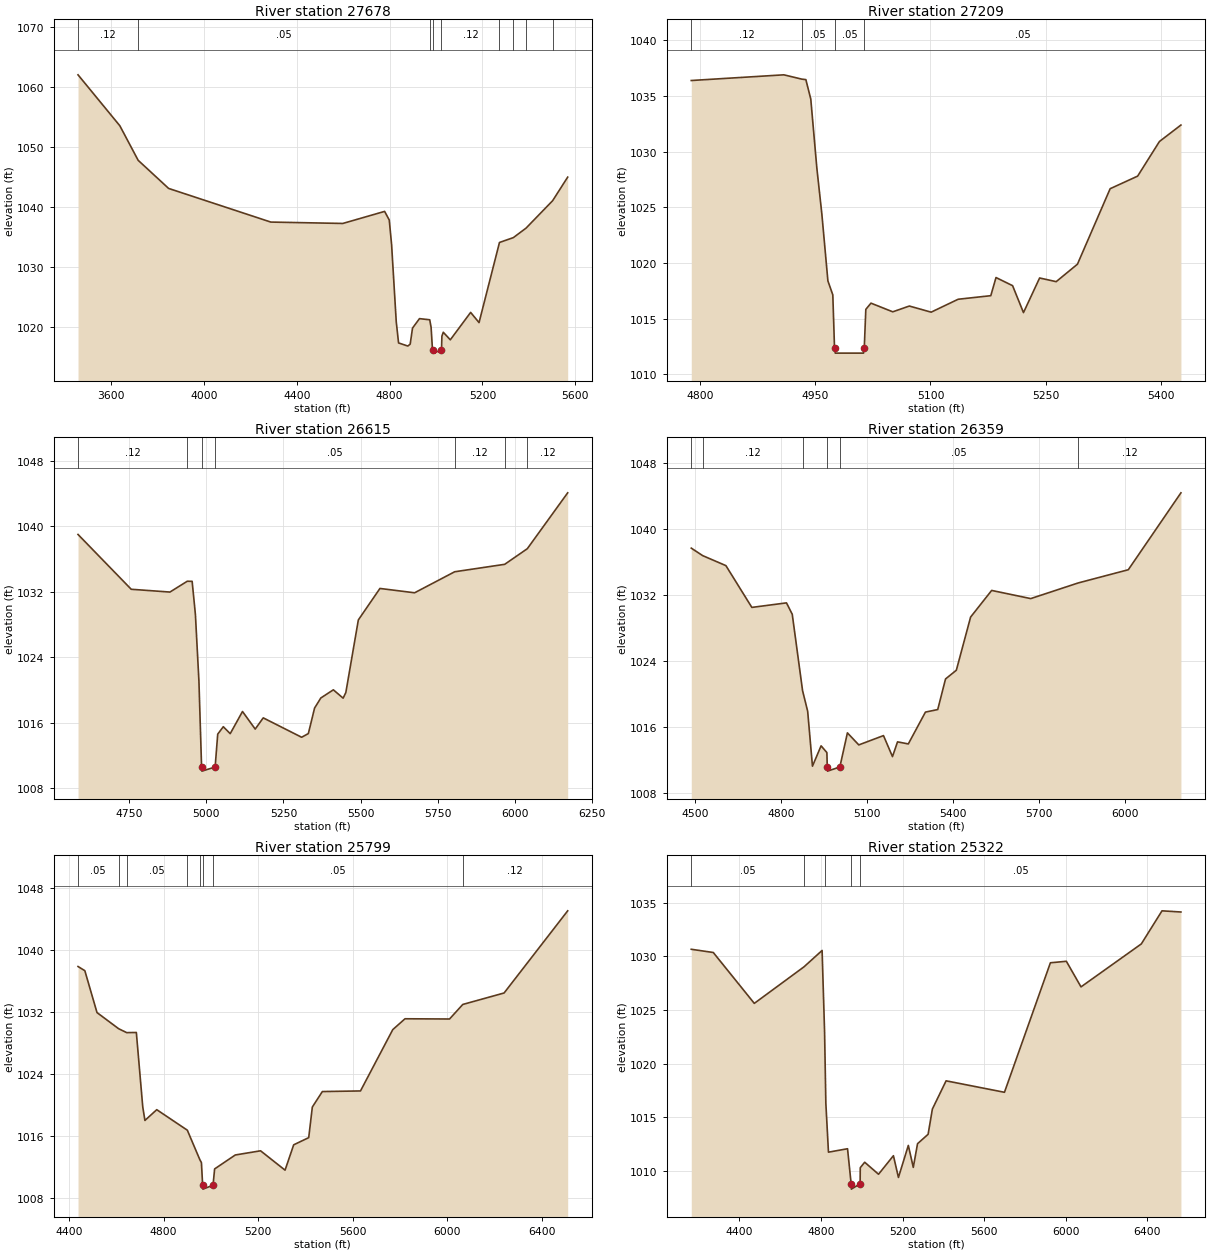
Type RM Length L Ch R = 1,27678,469,469,469
BEGIN DESCRIPTION:
LITTLE LLANO RIVER 49.0
END DESCRIPTION:
XS GIS Cut Line= 3
      2845005.68     10274353.11      2845082.00     10272812.00
      2844605.69     10272503.11
#Sta/Elev= 30
  3457.0 1062.06  3637.2 1053.57  3716.2 1047.81  3847.5 1043.12  4288.0 1037.51
  4598.4 1037.28  4778.6 1039.29  4798.6 1037.85  4808.7 1033.74  4828.7 1020.90
  4838.7 1017.36  4878.7 1016.84  4888.8 1017.16  4898.8 1019.83  4928.8 1021.41
  4973.0 1021.22  4978.9 1019.97  4985.0 1016.16  4986.0 1015.66  5023.7 1016.16
  5025.5 1018.48  5031.4 1019.14  5061.7 1017.88  5149.4 1022.45  5185.6 1020.75
  5273.7 1034.11  5333.5 1034.92  5388.2 1036.50  5502.7 1041.07  5567.7 1045.00
#Mann=9,-1,0
  3457.0    0.12       0  3716.2    0.05       0  4973.0    0.12       0
  4985.0    0.07       0  5023.7    0.12       0  5273.7    0.05       0
  5333.5    0.12       0  5388.2    0.05       0  5502.7    0.12       0
Bank Sta=4985,5023.7
Exp/Cntr=0.3,0.1

Type RM Length L Ch R = 1,27209,594,594,594
BEGIN DESCRIPTION:
LITTLE LLANO RIVER 48.0
END DESCRIPTION:
XS GIS Cut Line= 3
      2845655.68     10272753.11      2845492.00     10272619.00
      2845205.71     10272303.14
#Sta/Elev= 30
  4788.4 1036.39  4909.0 1036.90  4932.6 1036.51  4937.7 1036.47  4944.1 1034.72
  4952.0 1028.52  4958.5 1024.41  4966.4 1018.39  4972.8 1017.13  4975.0 1012.40
  4976.0 1011.90  5012.8 1011.90  5013.8 1012.40  5015.8 1015.83  5022.5 1016.39
  5050.9 1015.61  5072.5 1016.13  5100.9 1015.58  5136.1 1016.74  5178.6 1017.06
  5185.4 1018.69  5207.0 1017.96  5221.2 1015.54  5242.2 1018.65  5263.8 1018.32
  5291.5 1019.89  5334.1 1026.67  5369.9 1027.80  5398.3 1030.91  5426.3 1032.39
#Mann=4,-1,0
  4788.4    0.12       0  4932.6    0.05       0  4975.0    0.05       0
  5013.8    0.05       0
Bank Sta=4975,5013.8
Exp/Cntr=0.3,0.1

Type RM Length L Ch R = 1,26615,256,256,256
BEGIN DESCRIPTION:
LITTLE LLANO RIVER 47.0
END DESCRIPTION:
XS GIS Cut Line= 3
      2846205.72     10272253.12      2845812.25     10272119.00
      2844655.71     10272303.11
#Sta/Elev= 30
  4584.3 1039.02  4756.7 1032.32  4882.1 1031.98  4938.3 1033.30  4954.1 1033.29
  4964.7 1029.23  4976.1 1021.10  4984.7 1010.59  4985.7 1010.09  5028.6 1010.59
  5037.0 1014.61  5055.1 1015.52  5077.5 1014.67  5117.3 1017.38  5158.5 1015.23
  5184.5 1016.60  5308.9 1014.23  5330.7 1014.68  5350.9 1017.80  5371.1 1019.03
  5411.7 1020.03  5443.4 1019.01  5452.2 1019.70  5492.7 1028.57  5562.7 1032.42
  5675.0 1031.89  5804.9 1034.46  5967.0 1035.37  6040.3 1037.28  6171.1 1044.11
#Mann=7,-1,0
  4584.3    0.12       0  4938.3    0.05       0  4984.7    0.05       0
  5028.6    0.05       0  5804.9    0.12       0  5967.0    0.05       0
  6040.3    0.12       0
Bank Sta=4984.7,5028.6
Exp/Cntr=0.3,0.1

Type RM Length L Ch R = 1,26359,560,560,560
BEGIN DESCRIPTION:
LITTLE LLANO RIVER 46.0
END DESCRIPTION:
XS GIS Cut Line= 3
      2846305.71     10271953.11      2845795.50     10271896.00
      2844655.73     10272253.10
#Sta/Elev= 30
  4486.6 1037.73  4526.5 1036.82  4607.4 1035.61  4697.9 1030.54  4818.7 1031.09
  4838.8 1029.71  4874.8 1020.44  4892.6 1017.94  4909.3 1011.28  4939.4 1013.75
  4959.6 1012.93  4960.9 1011.18  4961.9 1010.68  5004.8 1011.18  5031.2 1015.32
  5070.9 1013.86  5157.0 1014.99  5188.4 1012.44  5206.0 1014.23  5243.6 1013.98
  5303.3 1017.84  5346.2 1018.15  5373.4 1021.86  5411.1 1022.92  5460.9 1029.37
  5534.3 1032.60  5670.5 1031.61  5836.4 1033.51  6010.8 1035.11  6194.4 1044.44
#Mann=6,-1,0
  4486.6    0.05       0  4526.5    0.12       0  4874.8    0.05       0
  4960.9    0.05       0  5004.8    0.05       0  5836.4    0.12       0
Bank Sta=4960.9,5004.8
Exp/Cntr=0.3,0.1

Type RM Length L Ch R = 1,25799,477,477,477
BEGIN DESCRIPTION:
LITTLE LLANO RIVER 45.0
END DESCRIPTION:
XS GIS Cut Line= 3
      2846355.72     10271703.13      2845883.00     10271399.00
      2844605.72     10272203.09
#Sta/Elev= 30
  4437.9 1037.89  4466.7 1037.35  4518.2 1031.94  4609.5 1029.86  4643.7 1029.35
  4684.6 1029.37  4711.7 1019.77  4720.9 1018.01  4770.9 1019.40  4900.3 1016.75
  4953.7 1012.91  4959.9 1012.57  4965.1 1009.64  4966.1 1009.14  5009.0 1009.64
  5015.8 1011.75  5103.2 1013.55  5210.1 1014.09  5313.7 1011.59  5350.2 1014.86
  5413.8 1015.79  5429.1 1019.74  5471.5 1021.74  5632.8 1021.82  5769.4 1029.74
  5821.2 1031.14  6009.5 1031.11  6065.6 1032.99  6240.3 1034.47  6509.3 1045.08
#Mann=8,-1,0
  4437.9    0.05       0  4609.5    0.12       0  4643.7    0.05       0
  4900.3    0.12       0  4953.7    0.05       0  4965.1    0.05       0
  5009.0    0.05       0  6065.6    0.12       0
Bank Sta=4965.1,5009
Exp/Cntr=0.3,0.1

Type RM Length L Ch R = 1,25322,1070,1070,1070
BEGIN DESCRIPTION:
Mapping XS 2b00403d
END DESCRIPTION:
XS GIS Cut Line= 4
      2846462.98     10270902.61      2845840.59     10270968.12
      2844743.24     10271279.31      2844221.00     10271638.35
#Sta/Elev= 30
  4164.0 1030.67  4271.9 1030.37  4473.0 1025.62  4716.5 1029.03  4805.3 1030.56
  4817.4 1023.01  4823.7 1016.30  4836.5 1011.73  4930.0 1012.05  4947.7 1008.78
  4948.7 1008.28  4991.7 1008.78  4992.4 1010.28  5014.1 1010.79  5081.9 1009.67
  5154.9 1011.40  5179.5 1009.37  5228.0 1012.36  5252.3 1010.31  5273.1 1012.52
  5325.0 1013.40  5345.8 1015.75  5413.1 1018.39  5699.2 1017.32  5924.4 1029.41
  6002.6 1029.55  6074.4 1027.16  6370.0 1031.17  6471.5 1034.26  6564.2 1034.15
#Mann=5,-1,0
  4164.0    0.05       0  4716.5    0.12       0  4817.4    0.05       0
  4947.7    0.05       0  4991.7    0.05       0
Bank Sta=4947.7,4991.7
Exp/Cntr=0.3,0.1