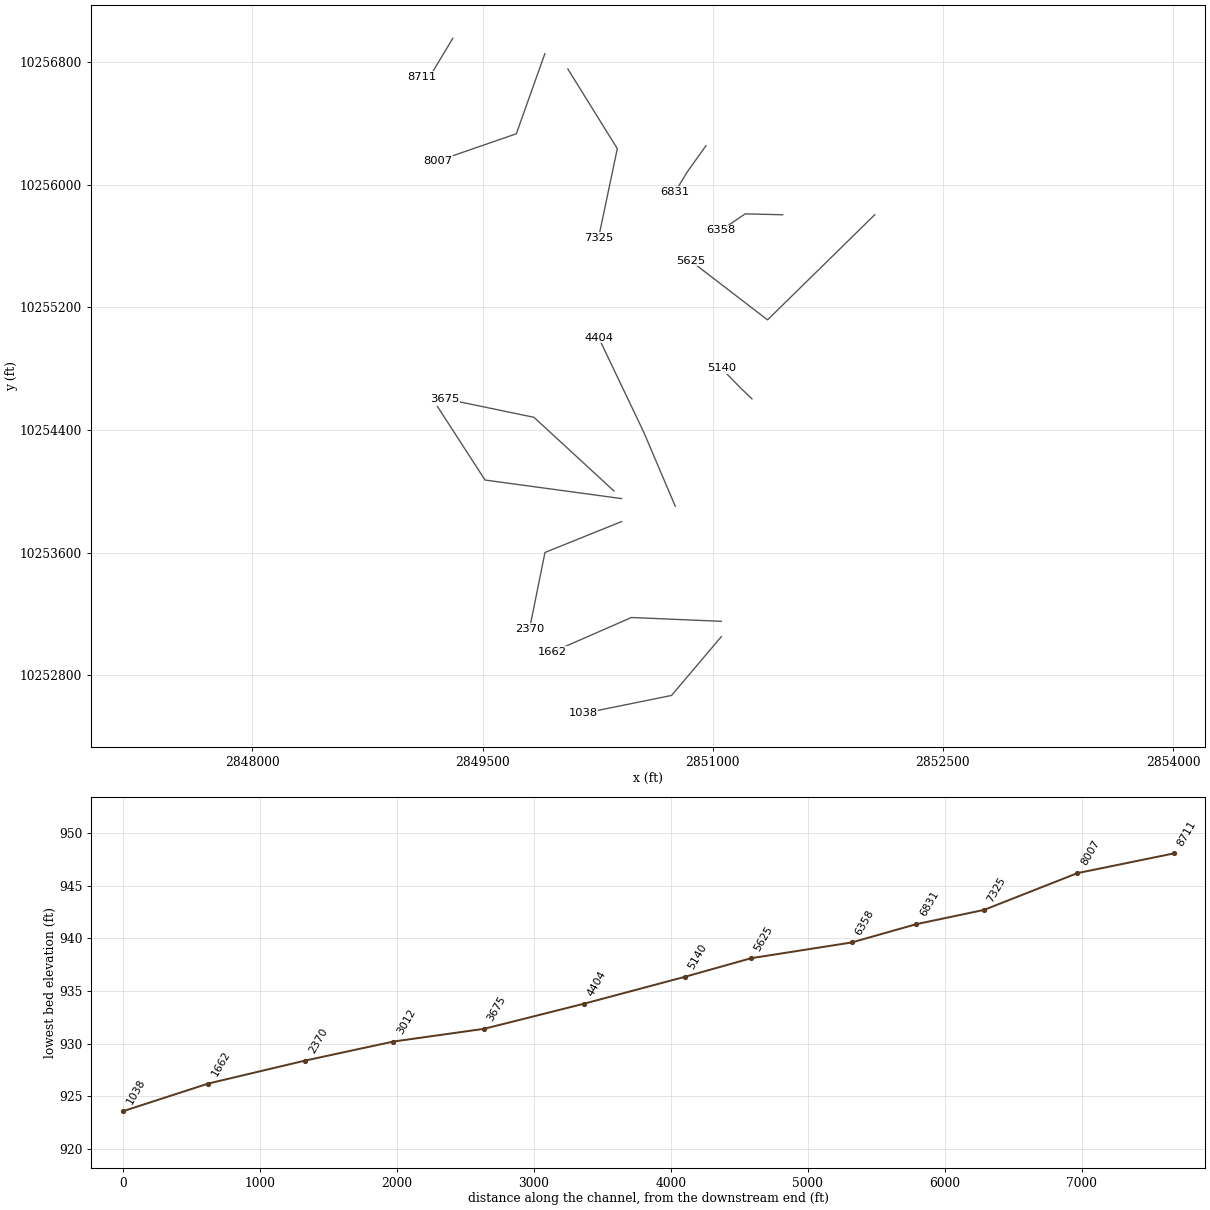
HEC-RAS study LITTLE LLANO RIVER.prj: LITTLE LLANO RIVER Base Level Engineering

--- LITTLE LLANO RIVER.g01 (geometry) --- (continued)

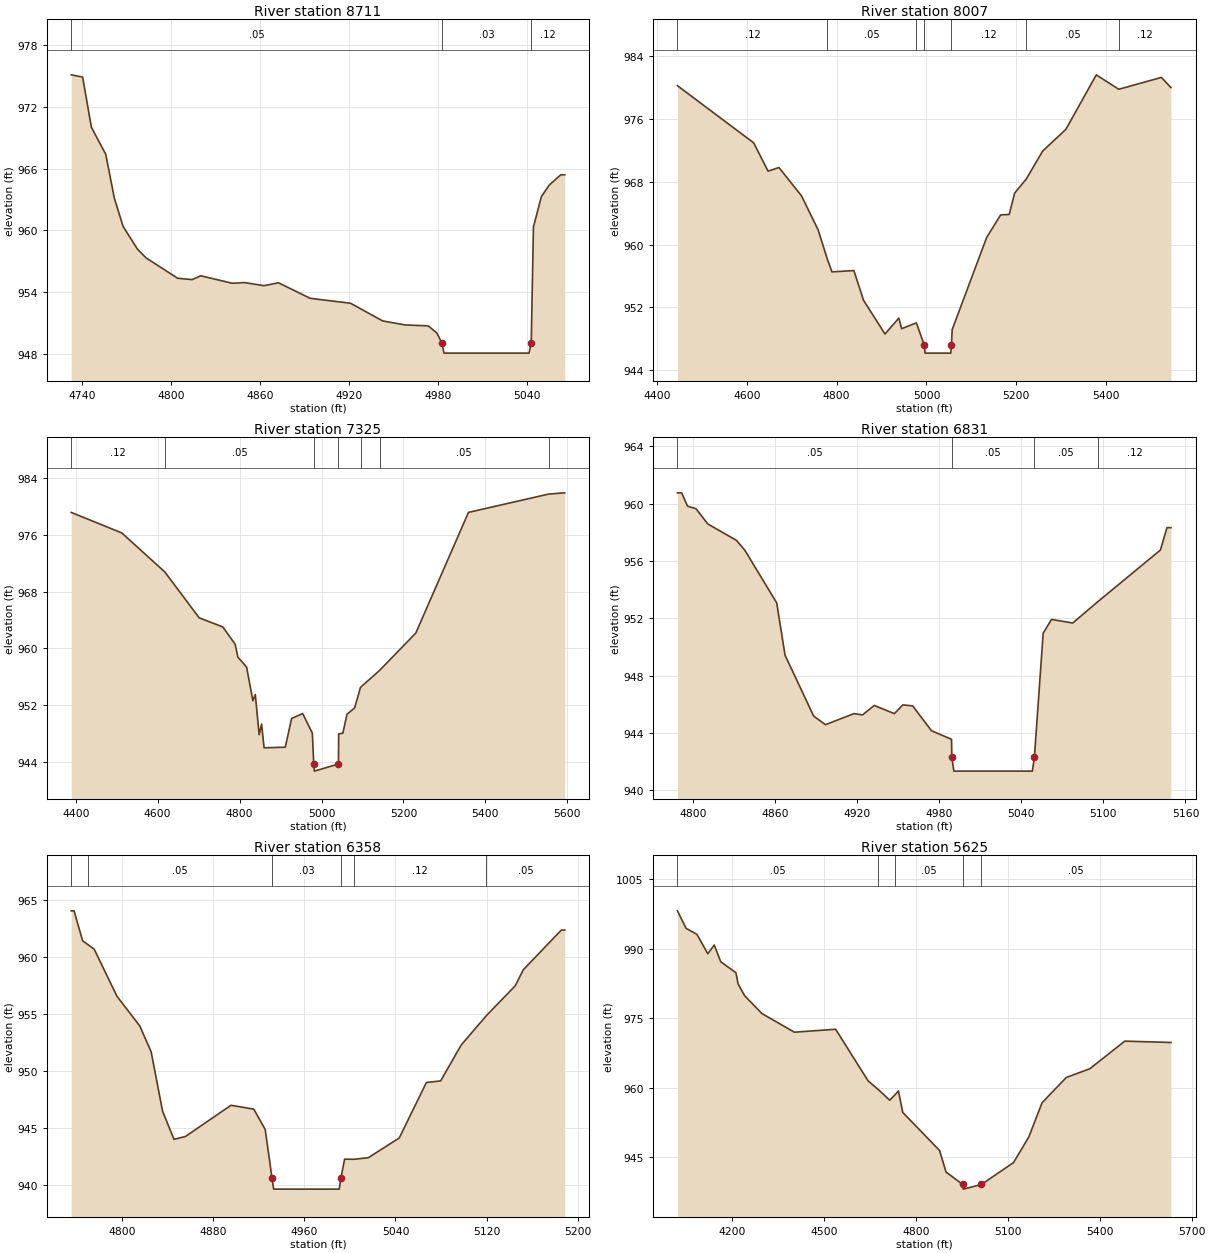
Type RM Length L Ch R = 1,8711,704,704,704
BEGIN DESCRIPTION:
LITTLE LLANO RIVER 13.0
END DESCRIPTION:
XS GIS Cut Line= 3
      2849305.67     10256953.09      2849167.75     10256724.00
      2849105.67     10256703.11
#Sta/Elev= 30
  4732.6  975.11  4740.3  974.89  4746.2  970.02  4755.9  967.38  4761.7  963.11
  4767.6  960.37  4777.2  958.18  4783.1  957.31  4804.4  955.33  4814.1  955.20
  4820.0  955.57  4841.3  954.84  4849.3  954.91  4862.7  954.61  4872.4  954.89
  4893.8  953.38  4921.0  952.90  4942.7  951.18  4957.9  950.79  4973.4  950.70
  4979.2  950.02  4982.6  949.05  4984.1  948.05  5041.4  948.05  5042.9  949.05
  5044.4  960.32  5049.7  963.25  5055.0  964.38  5062.8  965.39  5065.5  965.39
#Mann=3,-1,0
  4732.6    0.05       0  4982.6    0.03       0  5042.9    0.12       0
Bank Sta=4982.6,5042.9
Exp/Cntr=0.3,0.1

Type RM Length L Ch R = 1,8007,682,682,682
BEGIN DESCRIPTION:
LITTLE LLANO RIVER 12.0
END DESCRIPTION:
XS GIS Cut Line= 3
      2849905.67     10256853.08      2849719.75     10256331.00
      2849205.66     10256153.10
#Sta/Elev= 30
  4445.8  980.22  4615.6  972.94  4647.5  969.34  4671.7  969.80  4721.8  966.21
  4758.8  961.88  4779.6  958.11  4789.7  956.52  4838.5  956.69  4859.8  952.92
  4907.7  948.61  4938.5  950.64  4944.7  949.29  4977.5  950.03  4995.3  947.18
  4996.8  946.18  5054.1  946.18  5055.6  947.18  5057.2  949.17  5133.9  960.89
  5165.0  963.77  5184.2  963.83  5196.2  966.55  5222.0  968.33  5258.5  971.89
  5310.3  974.67  5377.9  981.60  5427.9  979.76  5522.8  981.27  5544.0  979.98
#Mann=7,-1,0
  4445.8    0.12       0  4779.6    0.05       0  4977.5    0.12       0
  4995.3    0.07       0  5055.6    0.12       0  5222.0    0.05       0
  5427.9    0.12       0
Bank Sta=4995.3,5055.6
Exp/Cntr=0.3,0.1

Type RM Length L Ch R = 1,7325,494,494,494
BEGIN DESCRIPTION:
LITTLE LLANO RIVER 11.0
END DESCRIPTION:
XS GIS Cut Line= 3
      2850055.70     10256753.08      2850378.00     10256234.00
      2850255.69     10255653.14
#Sta/Elev= 30
  4389.0  979.16  4512.4  976.27  4617.6  970.76  4701.3  964.30  4759.2  963.01
  4789.2  960.57  4795.8  958.76  4817.1  957.36  4832.4  952.61  4838.3  953.48
  4847.8  947.81  4853.7  949.32  4859.8  945.98  4911.5  946.06  4926.9  950.11
  4954.0  950.80  4977.5  948.05  4981.0  943.69  4982.5  942.69  5041.3  943.69
  5041.8  947.93  5052.0  948.04  5062.2  950.72  5080.8  951.60  5095.1  954.50
  5141.9  956.90  5230.2  962.16  5358.6  979.16  5554.8  981.75  5593.6  981.92
#Mann=7,-1,0
  4389.0    0.12       0  4617.6    0.05       0  4981.0    0.05       0
  5041.3    0.05       0  5095.1    0.12       0  5141.9    0.05       0
  5554.8    0.12       0
Bank Sta=4981,5041.3
Exp/Cntr=0.3,0.1

Type RM Length L Ch R = 1,6831,473,473,473
BEGIN DESCRIPTION:
LITTLE LLANO RIVER 10.0
END DESCRIPTION:
XS GIS Cut Line= 3
      2850955.71     10256253.14      2850833.00     10256081.00
      2850755.71     10255953.15
#Sta/Elev= 30
  4788.6  960.75  4791.7  960.75  4796.0  959.82  4802.2  959.64  4810.8  958.58
  4831.7  957.44  4837.8  956.76  4861.2  953.07  4867.3  949.42  4888.2  945.18
  4896.8  944.58  4917.7  945.35  4923.9  945.26  4932.5  945.92  4947.2  945.35
  4953.4  945.96  4960.6  945.89  4974.3  944.16  4989.0  943.56  4989.2  942.34
  4990.7  941.34  5048.1  941.34  5049.6  942.34  5056.0  950.96  5062.1  951.92
  5077.6  951.67  5096.1  953.17  5141.7  956.76  5146.5  958.32  5149.4  958.32
#Mann=4,-1,0
  4788.6    0.05       0  4989.2    0.05       0  5049.6    0.05       0
  5096.1    0.12       0
Bank Sta=4989.2,5049.6
Exp/Cntr=0.3,0.1

Type RM Length L Ch R = 1,6358,733,733,733
BEGIN DESCRIPTION:
LITTLE LLANO RIVER 9.0
END DESCRIPTION:
XS GIS Cut Line= 3
      2851455.73     10255803.11      2851211.50     10255809.00
      2851055.68     10255703.11
#Sta/Elev= 30
  4755.7  964.03  4758.2  964.03  4765.7  961.40  4770.4  961.06  4775.8  960.67
  4795.8  956.53  4815.8  953.93  4825.8  951.65  4835.8  946.44  4845.8  943.97
  4855.8  944.22  4895.8  946.96  4915.8  946.62  4925.8  944.83  4931.7  940.60
  4933.2  939.60  4990.7  939.60  4992.2  940.60  4995.4  942.23  5003.7  942.22
  5016.2  942.36  5043.3  944.09  5067.1  948.96  5079.6  949.10  5097.7  952.26
  5119.7  954.83  5145.0  957.45  5152.1  958.86  5185.4  962.34  5188.4  962.34
#Mann=6,-1,0
  4755.7    0.12       0  4770.4    0.05       0  4931.7    0.03       0
  4992.2    0.05       0  5003.7    0.12       0  5119.7    0.05       0
Bank Sta=4931.7,4992.2
Exp/Cntr=0.3,0.1

Type RM Length L Ch R = 1,5625,485,485,485
BEGIN DESCRIPTION:
LITTLE LLANO RIVER 8.0
END DESCRIPTION:
XS GIS Cut Line= 3
      2852055.71     10255803.14      2851357.25     10255118.00
      2850855.65     10255503.14
#Sta/Elev= 30
  4021.6  998.23  4049.9  994.45  4085.3  993.15  4120.6  988.97  4141.9  990.84
  4163.0  987.23  4212.6  984.86  4219.6  982.44  4240.9  979.90  4297.5  976.04
  4403.5  972.01  4537.9  972.65  4643.9  961.51  4677.7  959.59  4714.6  957.32
  4731.2  958.45  4742.9  959.33  4757.1  954.68  4877.2  946.46  4898.5  941.79
  4953.1  939.11  4954.6  938.11  5013.6  939.11  5118.4  943.84  5168.3  949.34
  5211.8  956.77  5290.7  962.22  5367.7  964.12  5481.9  970.08  5632.4  969.79
#Mann=5,-1,0
  4021.6    0.05       0  4677.7    0.12       0  4731.2    0.05       0
  4953.1    0.03       0  5013.6    0.05       0
Bank Sta=4953.1,5013.6
Exp/Cntr=0.3,0.1

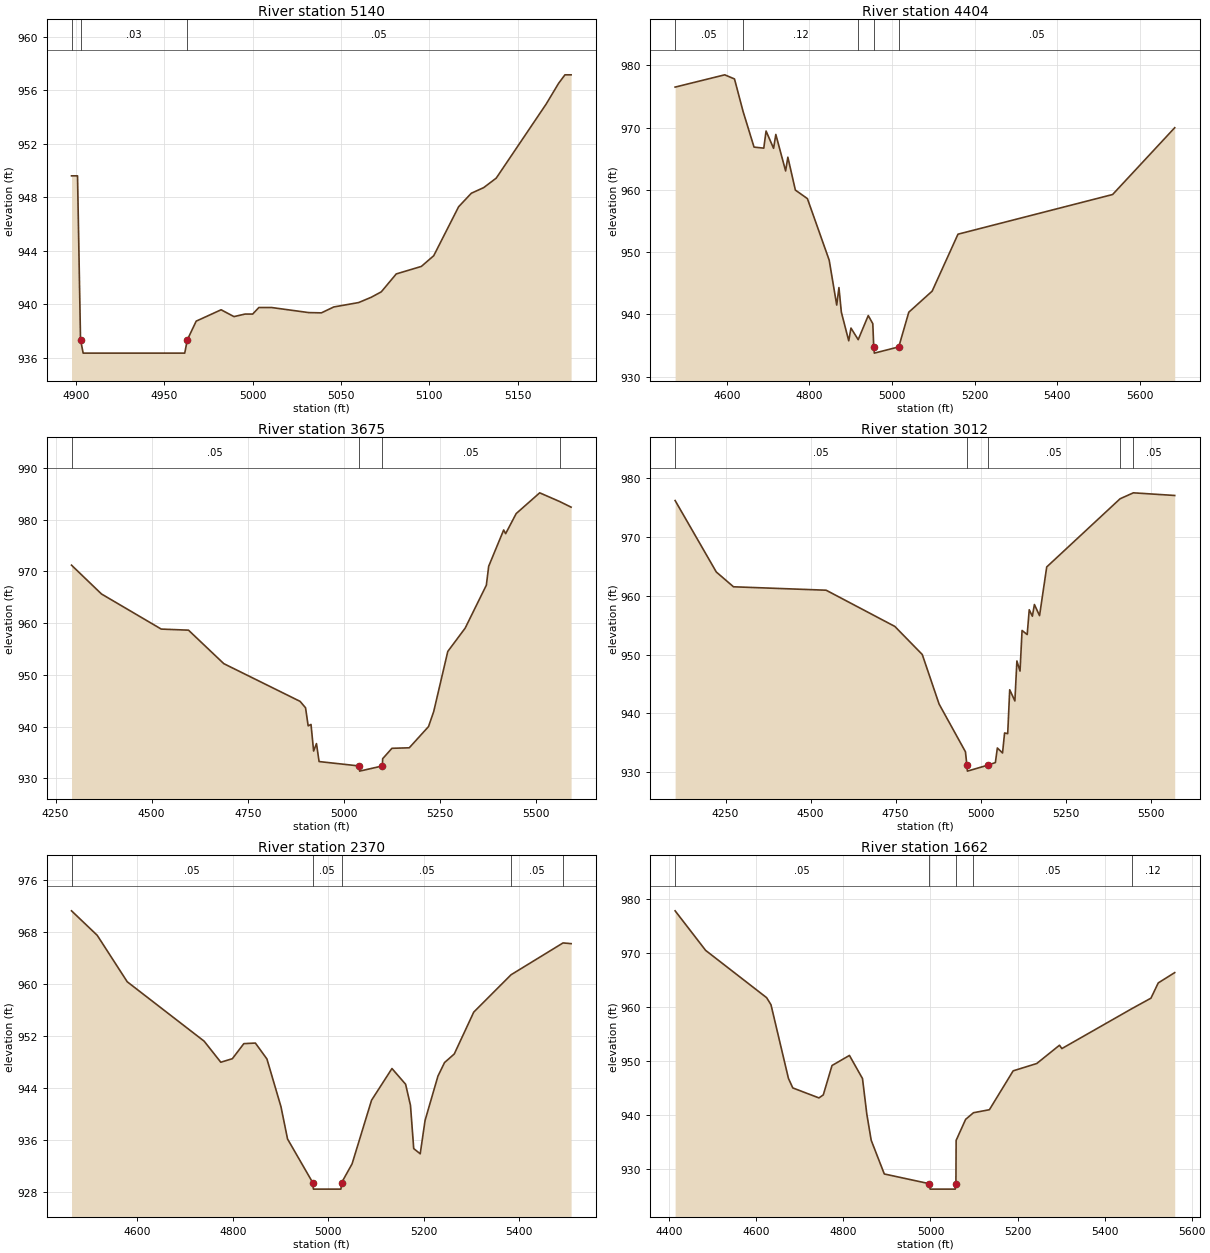
Type RM Length L Ch R = 1,5140,736,736,736
BEGIN DESCRIPTION:
LITTLE LLANO RIVER 7.0
END DESCRIPTION:
XS GIS Cut Line= 3
      2851255.68     10254603.12      2851181.50     10254674.00
      2851055.67     10254803.13
#Sta/Elev= 30
  4897.4  949.59  4900.8  949.59  4902.5  937.34  4904.0  936.34  4961.5  936.34
  4963.0  937.34  4968.0  938.73  4982.1  939.58  4989.4  939.07  4995.7  939.26
  5000.0  939.26  5003.5  939.75  5010.6  939.75  5031.7  939.37  5038.9  939.35
  5045.9  939.79  5060.0  940.12  5067.2  940.52  5072.8  940.92  5081.3  942.26
  5095.5  942.82  5102.5  943.62  5116.6  947.28  5123.8  948.29  5130.8  948.71
  5137.9  949.42  5166.2  954.96  5173.2  956.50  5176.8  957.14  5180.3  957.14
#Mann=3,-1,0
  4897.4    0.05       0  4902.5    0.03       0  4963.0    0.05       0
Bank Sta=4902.5,4963
Exp/Cntr=0.3,0.1

Type RM Length L Ch R = 1,4404,729,729,729
BEGIN DESCRIPTION:
LITTLE LLANO RIVER 6.0
END DESCRIPTION:
XS GIS Cut Line= 3
      2850755.70     10253903.08      2850550.25     10254386.00
      2850255.69     10255003.10
#Sta/Elev= 30
  4475.2  976.49  4595.2  978.46  4618.8  977.80  4639.6  972.58  4666.1  966.86
  4689.7  966.69  4695.2  969.44  4713.4  966.66  4718.8  968.89  4742.5  963.03
  4747.9  965.24  4766.1  959.96  4795.2  958.59  4847.9  948.72  4866.1  941.51
  4871.5  944.31  4877.3  940.37  4895.2  935.77  4900.6  937.81  4918.1  935.95
  4942.4  939.82  4953.4  938.52  4955.7  934.79  4957.2  933.79  5016.2  934.79
  5040.5  940.36  5097.0  943.74  5159.5  952.88  5533.6  959.25  5683.8  969.97
#Mann=5,-1,0
  4475.2    0.05       0  4639.6    0.12       0  4918.1    0.05       0
  4955.7    0.03       0  5016.2    0.05       0
Bank Sta=4955.7,5016.2
Exp/Cntr=0.3,0.1

Type RM Length L Ch R = 1,3675,663,663,663
BEGIN DESCRIPTION:
LITTLE LLANO RIVER 5.0
END DESCRIPTION:
XS GIS Cut Line= 3
      2850355.71     10254003.09      2849834.50     10254483.00
      2849255.73     10254603.10
#Sta/Elev= 30
  4291.5  971.21  4369.5  965.64  4524.9  958.86  4595.8  958.65  4687.6  952.18
  4886.1  944.89  4900.3  943.65  4907.1  940.16  4914.5  940.43  4921.3  935.29
  4928.7  936.73  4935.5  933.26  5039.5  932.41  5041.0  931.41  5100.1  932.41
  5100.9  933.81  5125.0  935.82  5170.1  935.92  5220.2  940.02  5233.7  942.93
  5270.3  954.54  5315.4  959.03  5370.6  967.34  5376.7  971.00  5415.7  978.01
  5420.8  977.30  5448.2  981.18  5509.4  985.19  5561.0  983.52  5591.1  982.42
#Mann=4,-1,0
  4291.5    0.05       0  5039.5    0.05       0  5100.1    0.05       0
  5561.0    0.12       0
Bank Sta=5039.5,5100.1
Exp/Cntr=0.3,0.1

Type RM Length L Ch R = 1,3012,642,642,642
BEGIN DESCRIPTION:
LITTLE LLANO RIVER 4.0
END DESCRIPTION:
XS GIS Cut Line= 3
      2850405.68     10253953.11      2849515.75     10254074.00
      2849205.68     10254553.12
#Sta/Elev= 30
  4101.9  976.16  4223.0  964.02  4273.5  961.51  4545.9  960.93  4747.8  954.78
  4828.5  950.01  4877.9  941.60  4955.5  933.48  4959.7  931.20  4961.2  930.20
  5020.3  931.20  5043.4  931.65  5049.3  934.13  5064.5  933.28  5070.5  936.68
  5079.7  936.57  5085.6  944.02  5100.8  942.12  5106.7  948.91  5115.9  947.19
  5121.9  954.09  5137.0  953.40  5143.0  957.61  5152.2  956.51  5158.2  958.50
  5173.3  956.61  5194.4  964.88  5410.1  976.46  5449.1  977.47  5570.7  977.02
#Mann=5,-1,0
  4101.9    0.05       0  4959.7    0.03       0  5020.3    0.05       0
  5410.1    0.12       0  5449.1    0.05       0
Bank Sta=4959.7,5020.3
Exp/Cntr=0.3,0.1

Type RM Length L Ch R = 1,2370,708,708,708
BEGIN DESCRIPTION:
LITTLE LLANO RIVER 3.0
END DESCRIPTION:
XS GIS Cut Line= 3
      2850405.71     10253803.12      2849906.50     10253602.00
      2849805.68     10253103.09
#Sta/Elev= 30
  4461.8  971.23  4515.7  967.46  4578.6  960.31  4739.8  951.17  4774.7  947.93
  4798.9  948.47  4823.0  950.79  4847.2  950.88  4871.4  948.43  4900.9  941.07
  4914.6  936.12  4967.4  929.40  4968.9  928.40  5026.5  928.40  5028.0  929.40
  5049.9  932.29  5090.7  942.08  5133.5  946.96  5162.1  944.54  5172.3  941.29
  5179.1  934.64  5192.7  933.84  5202.9  938.98  5229.9  945.80  5243.7  947.88
  5264.1  949.20  5304.9  955.64  5383.1  961.39  5492.1  966.29  5509.0  966.18
#Mann=5,-1,0
  4461.8    0.05       0  4967.4    0.05       0  5028.0    0.05       0
  5383.1    0.05       0  5492.1    0.12       0
Bank Sta=4967.4,5028
Exp/Cntr=0.3,0.1

Type RM Length L Ch R = 1,1662,624,624,624
BEGIN DESCRIPTION:
LITTLE LLANO RIVER 2.0
END DESCRIPTION:
XS GIS Cut Line= 3
      2851055.72     10253153.11      2850469.75     10253178.00
      2849955.69     10252953.11
#Sta/Elev= 30
  4413.5  977.84  4483.6  970.50  4623.7  961.73  4633.7  960.42  4673.8  946.76
  4683.8  944.99  4743.8  943.14  4753.8  943.69  4773.9  949.15  4813.9  951.02
  4843.9  946.73  4853.9  940.09  4863.9  935.28  4894.0  929.03  4997.8  927.22
  4999.3  926.22  5057.0  926.22  5058.5  927.22  5059.0  935.26  5080.8  939.16
  5098.8  940.39  5135.4  940.95  5190.0  948.16  5244.2  949.52  5296.4  952.91
  5301.9  952.29  5462.8  959.70  5506.5  961.64  5523.3  964.47  5561.1  966.38
#Mann=5,-1,0
  4413.5    0.05       0  4997.8    0.05       0  5058.5    0.05       0
  5098.8    0.05       0  5462.8    0.12       0
Bank Sta=4997.8,5058.5
Exp/Cntr=0.3,0.1

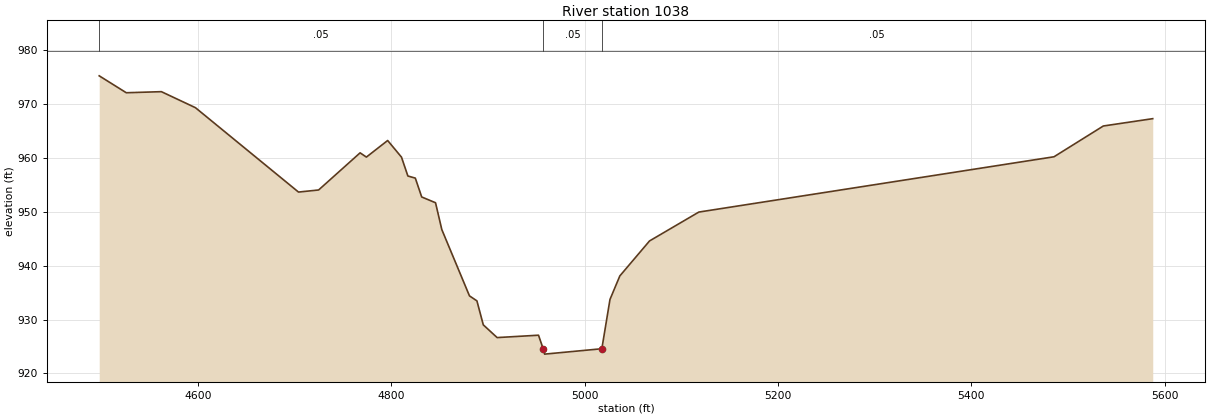
Type RM Length L Ch R = 1,1038,0,0,0
BEGIN DESCRIPTION:
LITTLE LLANO RIVER 1.0
END DESCRIPTION:
XS GIS Cut Line= 3
      2851055.71     10253053.14      2850731.50     10252670.00
      2850155.64     10252553.10
#Sta/Elev= 30
  4498.1  975.23  4526.1  972.09  4562.4  972.29  4597.6  969.32  4704.2  953.66
  4725.0  954.05  4767.9  960.94  4774.4  960.15  4796.4  963.23  4810.7  960.14
  4817.3  956.64  4825.0  956.25  4831.6  952.75  4845.9  951.68  4852.4  946.70
  4881.0  934.40  4888.7  933.47  4895.3  929.02  4909.6  926.66  4952.4  927.10
  4957.2  924.59  4958.7  923.59  5017.9  924.59  5026.3  933.73  5036.5  938.10
  5067.2  944.59  5118.2  949.95  5485.5  960.21  5536.5  965.92  5587.6  967.28
#Mann=3,-1,0
  4498.1    0.05       0  4957.2    0.05       0  5017.9    0.05       0
Bank Sta=4957.2,5017.9
Exp/Cntr=0.3,0.1

Chan Stop Cuts=-1