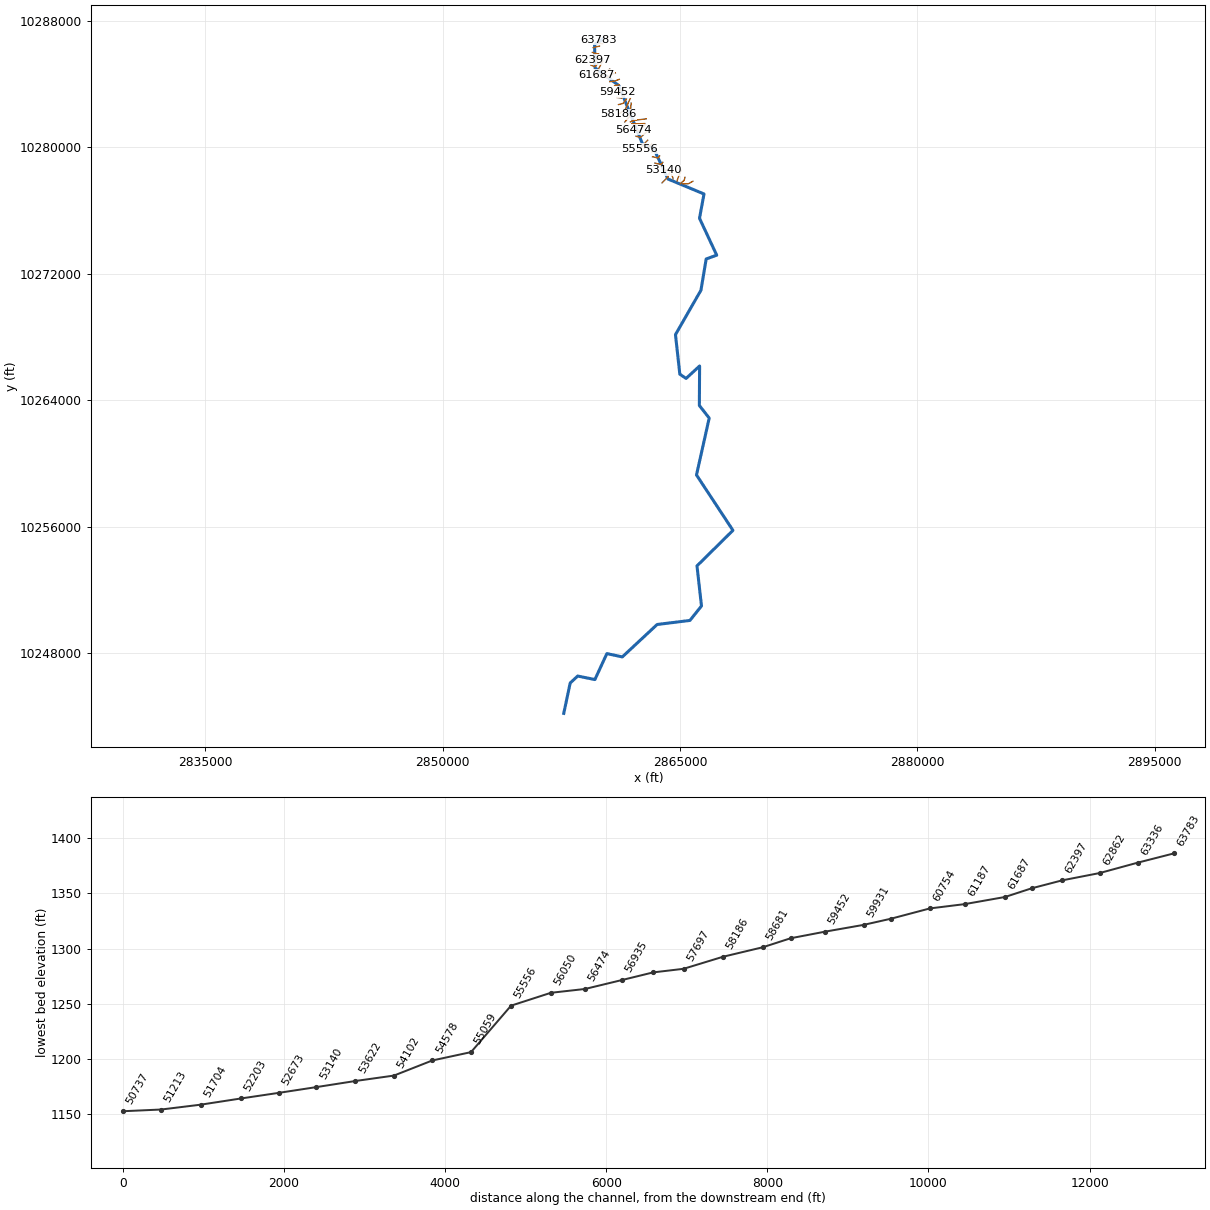
--- MILLER CREEK.prj (project) ---

Proj Title=MILLER CREEK Base Level Engineering
Current Plan=p01
Default Exp/Contr=0.3,0.1
English Units
Geom File=g01
Flow File=f01
Plan File=p01
BEGIN DESCRIPTION:
MILLER CREEK
END DESCRIPTION:

--- MILLER CREEK.p01 (plan) ---

Plan Title=Multiple Run
Short Identifier=Multiple
Geom File=g01
Flow File=f01
Subcritical Flow
K Sum by GR= 0
Std Step Tol= 0.01
Critical Tol= 0.01
Num of Std Step Trials= 20
Max Error Tol= 0.3
Flow Tol Ratio= 0.001
Split Flow NTrial= 30
Split Flow Tol= 0.02
Split Flow Ratio= 0.02
Log Output Level= 0
Friction Slope Method= 1
Unsteady Friction Slope Method= 2
Unsteady Bridges Friction Slope Method= 1
Parabolic Critical Depth
Global Vel Dist=  1 , 1 , 1
Global Log Level= 0
CheckData=True
Encroach Param= -1, 0, 0, 0
BEGIN DESCRIPTION:
Multiple Run
END DESCRIPTION:

--- MILLER CREEK.f01 (steady flow) ---

Flow Title=Multiple
Number of Profiles=7
Profile Names=10-year,25-year,50-year,1pct_min,100-year,1pct_plu,500-year
River Rch & RM= MILLER CREEK,Reach-1,63783
      69     130     201     104     313     946     822
River Rch & RM= MILLER CREEK,Reach-1,57697
     109     221     354     188     567    1713    1556
River Rch & RM= MILLER CREEK,Reach-1,51213
     145     304     496     267     805    2431    2260
River Rch & RM= MILLER CREEK,Reach-1,47911
     173     374     616     334    1009    3046    2873
River Rch & RM= MILLER CREEK,Reach-1,37600
     203     444     737     402    1214    3666    3496
River Rch & RM= MILLER CREEK,Reach-1,28136
     222     490     817     447    1350    4077    3912
River Rch & RM= MILLER CREEK,Reach-1,19858
     279     626    1054     580    1753    5293    5148
River Rch & RM= MILLER CREEK,Reach-1,17373
     316     715    1208     668    2017    6092    5967
River Rch & RM= MILLER CREEK,Reach-1,9874
     359     818    1388     770    2326    7026    6929
River Rch & RM= MILLER CREEK,Reach-1,7643
     465    1075    1839    1027    3103    9370    9363
River Rch & RM= MILLER CREEK,Reach-1,4757
     484    1122    1921    1074    3244    9797    9808
Boundary for River Rch & Prof#=MILLER CREEK,Reach-1,1
Up Type=0
Dn Type=3
Dn Slope=0.005
Boundary for River Rch & Prof#=MILLER CREEK,Reach-1,2
Up Type=0
Dn Type=3
Dn Slope=0.005
Boundary for River Rch & Prof#=MILLER CREEK,Reach-1,3
Up Type=0
Dn Type=3
Dn Slope=0.005
Boundary for River Rch & Prof#=MILLER CREEK,Reach-1,4
Up Type=0
Dn Type=3
Dn Slope=0.005
Boundary for River Rch & Prof#=MILLER CREEK,Reach-1,5
Up Type=0
Dn Type=3
Dn Slope=0.005
Boundary for River Rch & Prof#=MILLER CREEK,Reach-1,6
Up Type=0
Dn Type=3
Dn Slope=0.005
Boundary for River Rch & Prof#=MILLER CREEK,Reach-1,7
Up Type=0
Dn Type=3
Dn Slope=0.005

--- MILLER CREEK.g01 (geometry) ---

Geom Title=Existing Conditions

River Reach=MILLER CREEK,Reach-1
Reach XY= 30
      2860165.50     10286894.00      2859594.00     10286484.00
      2859622.50     10285024.00      2861124.75     10283908.00
      2862631.50     10280195.00      2863294.00     10280001.00
      2864234.50     10277995.00      2866509.50     10277050.00
      2866225.25     10275513.00      2867312.75     10273179.00
      2866647.00     10272938.00      2866315.75     10270960.00
      2864706.50     10268154.00      2864981.50     10265651.00
      2865375.25     10265382.00      2866231.50     10266170.00
      2866215.75     10263670.00      2866837.75     10262876.00
      2866034.50     10259276.00      2868339.00     10255773.00
      2866065.75     10253526.00      2866350.25     10250991.00
      2865619.00     10250076.00      2863547.00     10249820.00
      2861346.75     10247769.00      2860369.75     10247979.00
      2859614.25     10246337.00      2858526.75     10246559.00
      2858051.75     10246118.00      2857645.50     10244198.00

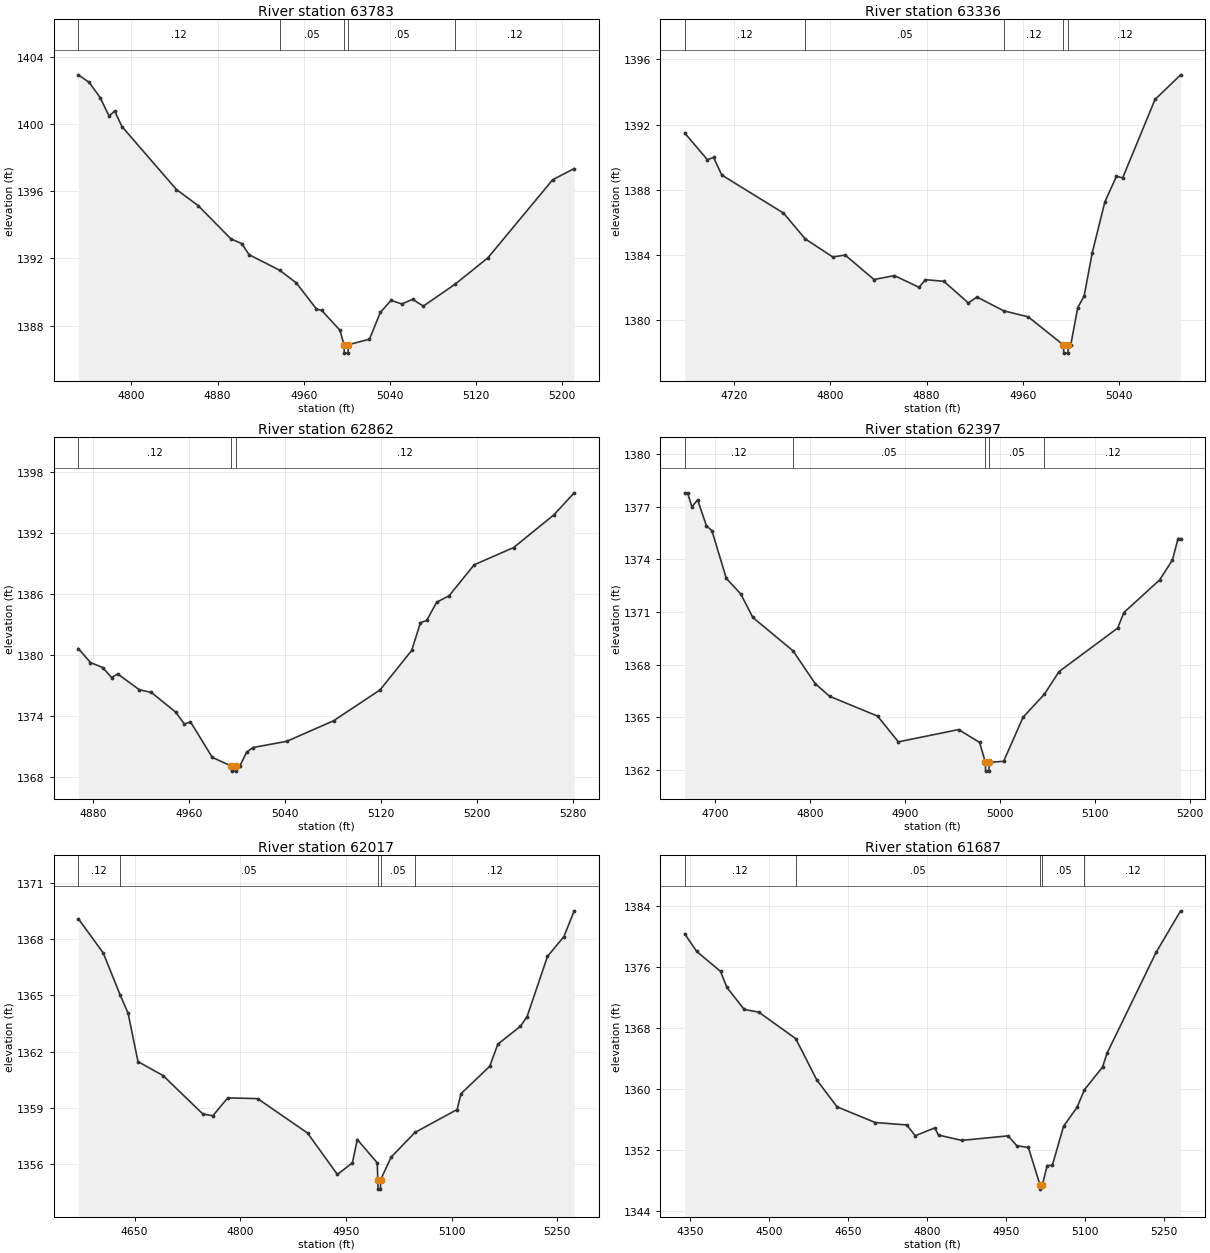
Type RM Length L Ch R = 1,63783,447,447,447
BEGIN DESCRIPTION:
MILLER CREEK 120.0
END DESCRIPTION:
XS GIS Cut Line= 3
      2860105.65     10286553.12      2859859.50     10286592.00
      2859855.69     10286803.07
#Sta/Elev= 30
  4750.8 1402.93  4760.9 1402.48  4771.0 1401.58  4779.4 1400.47  4784.5 1400.78
  4791.3 1399.85  4841.9 1396.10  4862.1 1395.14  4892.5 1393.16  4902.6 1392.88
  4909.3 1392.22  4937.6 1391.30  4953.2 1390.54  4971.8 1388.99  4976.8 1388.90
  4993.7 1387.72  4997.4 1386.86  4997.7 1386.36  5001.2 1386.36  5001.4 1386.86
  5021.1 1387.19  5031.1 1388.78  5041.1 1389.50  5051.1 1389.29  5061.1 1389.56
  5071.1 1389.16  5100.9 1390.48  5131.1 1392.04  5191.1 1396.68  5211.1 1397.35
#Mann=5,-1,0
  4750.8    0.12       0  4937.6    0.05       0  4997.4    0.05       0
  5001.4    0.05       0  5100.9    0.12       0
Bank Sta=4997.4,5001.4
Exp/Cntr=0.3,0.1

Type RM Length L Ch R = 1,63336,474,474,474
BEGIN DESCRIPTION:
MILLER CREEK 119.0
END DESCRIPTION:
XS GIS Cut Line= 3
      2859905.65     10286403.10      2859592.75     10286331.00
      2859505.71     10286303.12
#Sta/Elev= 30
  4678.9 1391.48  4697.7 1389.85  4702.8 1389.99  4709.7 1388.91  4761.0 1386.58
  4779.1 1385.00  4802.0 1383.89  4812.3 1384.01  4836.3 1382.51  4853.3 1382.75
  4873.8 1382.03  4879.1 1382.50  4894.4 1382.40  4914.9 1381.07  4921.9 1381.44
  4944.3 1380.59  4964.7 1380.22  4993.9 1378.50  4994.2 1378.00  4997.7 1378.00
  4997.9 1378.50  5000.0 1378.50  5005.8 1380.79  5011.1 1381.49  5017.9 1384.16
  5028.4 1387.27  5038.0 1388.83  5043.2 1388.74  5070.1 1393.54  5091.4 1395.05
#Mann=5,-1,0
  4678.9    0.12       0  4779.1    0.05       0  4944.3    0.12       0
  4993.9    0.07       0  4997.9    0.12       0
Bank Sta=4993.9,4997.9
Exp/Cntr=0.3,0.1

Type RM Length L Ch R = 1,62862,465,465,465
BEGIN DESCRIPTION:
MILLER CREEK 118.0
END DESCRIPTION:
XS GIS Cut Line= 3
      2859855.67     10285903.11      2859725.50     10285925.00
      2859455.68     10286003.11
#Sta/Elev= 30
  4868.0 1380.60  4878.1 1379.22  4888.3 1378.73  4895.7 1377.74  4900.8 1378.10
  4918.7 1376.55  4928.8 1376.28  4949.1 1374.34  4956.3 1373.17  4961.4 1373.39
  4979.5 1369.90  4995.4 1369.04  4995.6 1368.54  4999.1 1368.54  4999.4 1369.04
  5002.5 1369.04  5008.1 1370.40  5013.3 1370.86  5041.5 1371.47  5080.5 1373.49
  5119.3 1376.53  5145.6 1380.41  5152.9 1383.14  5158.1 1383.36  5166.4 1385.15
  5176.8 1385.79  5197.6 1388.83  5230.5 1390.53  5264.1 1393.75  5280.9 1395.91
#Mann=3,-1,0
  4868.0    0.12       0  4995.4    0.07       0  4999.4    0.12       0
Bank Sta=4995.4,4999.4
Exp/Cntr=0.3,0.1

Type RM Length L Ch R = 1,62397,380,380,380
BEGIN DESCRIPTION:
MILLER CREEK 117.0
END DESCRIPTION:
XS GIS Cut Line= 3
      2859905.65     10285653.09      2859627.75     10285472.00
      2859455.71     10285553.10
#Sta/Elev= 30
  4668.3 1377.80  4671.2 1377.80  4675.8 1377.00  4681.8 1377.40  4691.0 1375.93
  4696.9 1375.63  4712.0 1372.92  4727.2 1372.03  4739.9 1370.69  4782.3 1368.78
  4805.6 1366.91  4820.7 1366.19  4871.2 1365.06  4893.1 1363.59  4956.4 1364.29
  4978.6 1363.56  4984.7 1362.42  4984.9 1361.92  4988.4 1361.92  4988.7 1362.42
  5003.9 1362.48  5024.4 1365.00  5046.8 1366.31  5062.2 1367.60  5123.9 1370.08
  5130.5 1370.97  5168.1 1372.83  5181.6 1373.97  5187.5 1375.19  5190.2 1375.19
#Mann=5,-1,0
  4668.3    0.12       0  4782.3    0.05       0  4984.7    0.05       0
  4988.7    0.05       0  5046.8    0.12       0
Bank Sta=4984.7,4988.7
Exp/Cntr=0.3,0.1

Type RM Length L Ch R = 1,62017,330,330,330
BEGIN DESCRIPTION:
MILLER CREEK 116.0
END DESCRIPTION:
XS GIS Cut Line= 3
      2859905.66     10285403.08      2859607.00     10285094.00
      2859355.67     10285203.12
#Sta/Elev= 30
  4570.2 1369.08  4605.5 1367.26  4629.8 1365.00  4640.8 1364.05  4654.9 1361.47
  4690.4 1360.73  4747.0 1358.68  4761.2 1358.59  4782.3 1359.54  4824.7 1359.50
  4895.5 1357.67  4937.9 1355.46  4959.2 1356.08  4966.2 1357.32  4994.5 1356.08
  4995.3 1355.18  4995.6 1354.68  4999.1 1354.68  4999.3 1355.18  5014.1 1356.38
  5048.1 1357.70  5107.9 1358.92  5113.3 1359.76  5154.1 1361.22  5165.7 1362.40
  5197.7 1363.35  5207.2 1363.87  5236.1 1367.07  5259.5 1368.13  5274.0 1369.50
#Mann=5,-1,0
  4570.2    0.12       0  4629.8    0.05       0  4995.3    0.05       0
  4999.3    0.05       0  5048.1    0.12       0
Bank Sta=4995.3,4999.3
Exp/Cntr=0.3,0.1

Type RM Length L Ch R = 1,61687,500,500,500
BEGIN DESCRIPTION:
MILLER CREEK 115.0
END DESCRIPTION:
XS GIS Cut Line= 3
      2860105.70     10285453.15      2859798.50     10284869.00
      2859705.69     10284603.13
#Sta/Elev= 30
  4340.0 1380.32  4362.6 1378.03  4407.8 1375.41  4420.0 1373.30  4452.8 1370.41
  4480.5 1370.05  4550.6 1366.58  4590.7 1361.14  4629.1 1357.62  4701.6 1355.56
  4761.4 1355.24  4777.7 1353.82  4814.6 1354.85  4821.8 1353.91  4865.9 1353.21
  4954.1 1353.81  4970.5 1352.51  4992.5 1352.28  5014.8 1347.31  5015.1 1346.81
  5018.8 1347.31  5028.2 1349.91  5038.0 1349.93  5059.3 1355.07  5085.0 1357.56
  5098.9 1359.86  5133.3 1362.84  5141.9 1364.67  5235.0 1377.90  5281.6 1383.36
#Mann=5,-1,0
  4340.0    0.12       0  4550.6    0.05       0  5014.8    0.05       0
  5018.8    0.05       0  5098.9    0.12       0
Bank Sta=5014.8,5018.8
Exp/Cntr=0.3,0.1

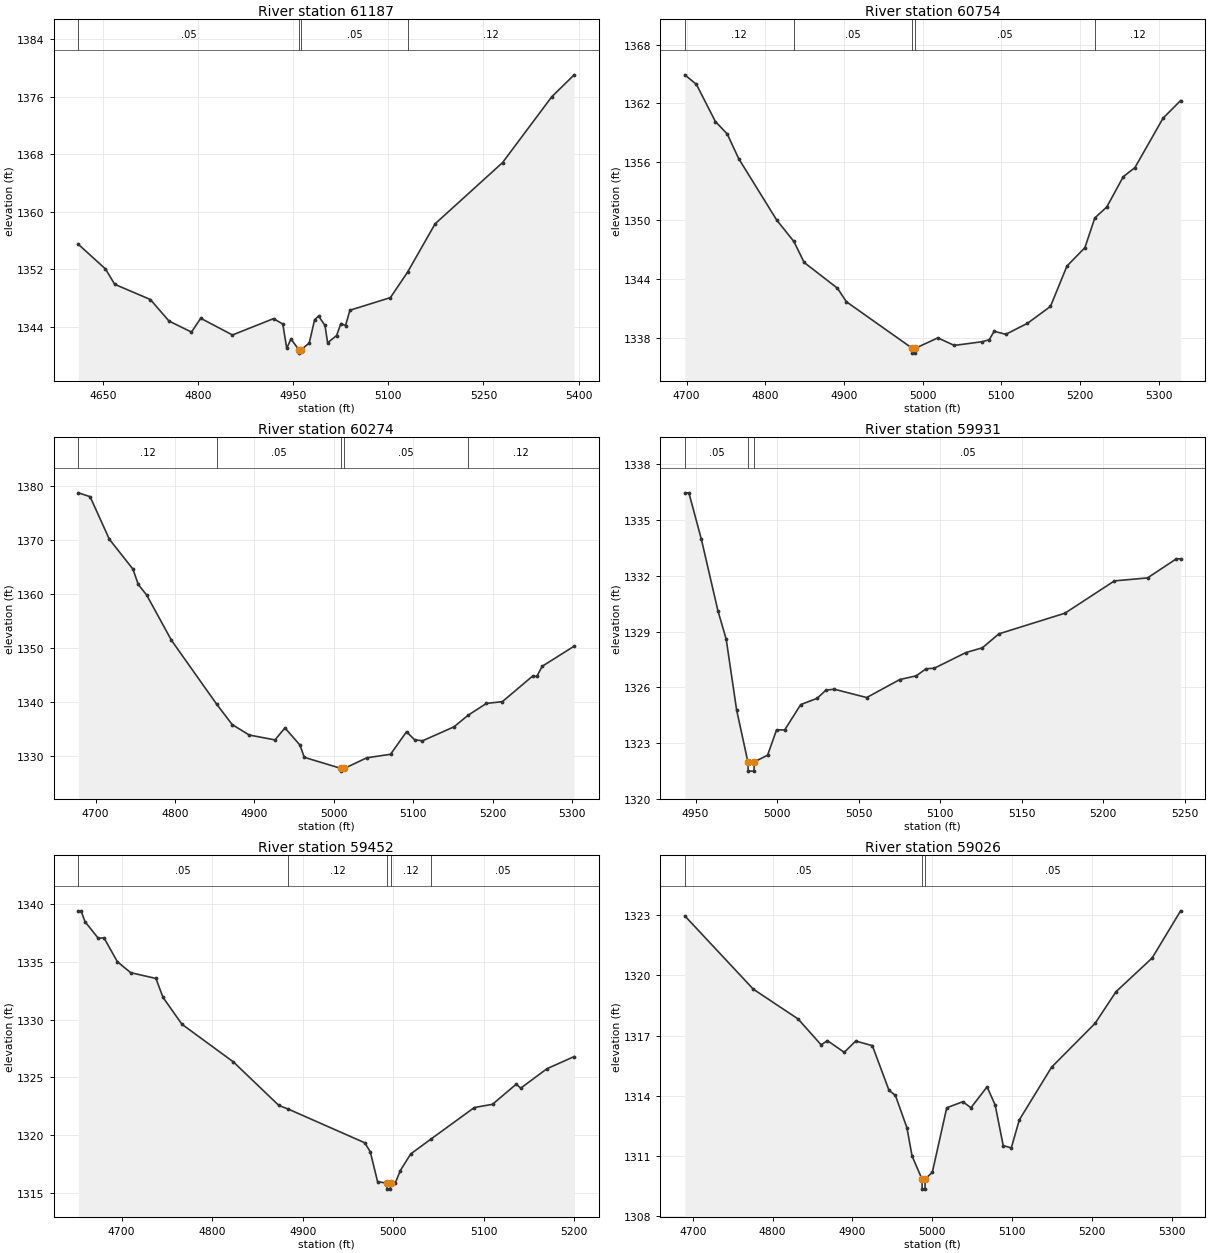
Type RM Length L Ch R = 1,61187,433,433,433
BEGIN DESCRIPTION:
MILLER CREEK 114.0
END DESCRIPTION:
XS GIS Cut Line= 3
      2860555.66     10284953.10      2860242.50     10284722.00
      2859955.72     10284453.14
#Sta/Elev= 30
  4610.8 1355.49  4653.6 1352.06  4668.2 1349.92  4724.5 1347.80  4753.8 1344.81
  4789.3 1343.27  4803.9 1345.19  4854.0 1342.87  4918.8 1345.14  4933.4 1344.39
  4939.6 1341.02  4946.3 1342.30  4958.5 1340.84  4958.7 1340.34  4962.5 1340.84
  4975.1 1341.74  4983.6 1344.99  4989.8 1345.50  5000.0 1344.19  5004.1 1341.78
  5018.3 1342.79  5025.1 1344.46  5032.4 1344.18  5039.3 1346.31  5103.2 1348.07
  5130.3 1351.62  5173.8 1358.35  5280.1 1366.86  5357.7 1376.02  5393.1 1379.08
#Mann=4,-1,0
  4610.8    0.05       0  4958.5    0.05       0  4962.5    0.05       0
  5130.3    0.12       0
Bank Sta=4958.5,4962.5
Exp/Cntr=0.3,0.1

Type RM Length L Ch R = 1,60754,480,480,480
BEGIN DESCRIPTION:
MILLER CREEK 113.0
END DESCRIPTION:
XS GIS Cut Line= 3
      2860905.70     10284703.12      2860625.25     10284590.00
      2860355.70     10284403.12
#Sta/Elev= 30
  4697.6 1364.90  4712.4 1363.92  4736.5 1360.12  4751.5 1358.86  4766.1 1356.33
  4814.4 1350.05  4836.3 1347.85  4849.3 1345.71  4891.7 1343.07  4903.0 1341.69
  4986.7 1336.93  4987.0 1336.43  4990.5 1336.43  4990.7 1336.93  5019.3 1337.99
  5040.2 1337.22  5076.0 1337.60  5084.6 1337.80  5090.9 1338.66  5105.8 1338.36
  5133.3 1339.48  5162.5 1341.21  5183.5 1345.34  5206.3 1347.22  5218.9 1350.26
  5234.1 1351.38  5255.1 1354.48  5269.9 1355.41  5305.7 1360.47  5328.0 1362.27
#Mann=5,-1,0
  4697.6    0.12       0  4836.3    0.05       0  4986.7    0.05       0
  4990.7    0.05       0  5218.9    0.12       0
Bank Sta=4986.7,4990.7
Exp/Cntr=0.3,0.1

Type RM Length L Ch R = 1,60274,343,343,343
BEGIN DESCRIPTION:
MILLER CREEK 112.0
END DESCRIPTION:
XS GIS Cut Line= 3
      2861155.69     10284303.12      2860856.75     10284184.00
      2860555.73     10284153.12
#Sta/Elev= 30
  4678.2 1378.65  4693.0 1377.94  4717.3 1370.05  4747.0 1364.53  4753.6 1361.71
  4764.3 1359.72  4795.5 1351.35  4852.6 1339.49  4872.0 1335.75  4893.5 1333.82
  4925.8 1332.92  4938.4 1335.14  4957.3 1331.96  4962.7 1329.70  5009.1 1327.64
  5009.4 1327.14  5013.1 1327.64  5041.3 1329.60  5071.4 1330.26  5091.5 1334.43
  5101.6 1332.96  5111.6 1332.75  5151.3 1335.34  5169.1 1337.49  5192.1 1339.67
  5212.2 1340.00  5250.5 1344.76  5255.5 1344.66  5262.4 1346.55  5302.6 1350.27
#Mann=5,-1,0
  4678.2    0.12       0  4852.6    0.05       0  5009.1    0.05       0
  5013.1    0.05       0  5169.1    0.12       0
Bank Sta=5009.1,5013.1
Exp/Cntr=0.3,0.1

Type RM Length L Ch R = 1,59931,479,479,479
BEGIN DESCRIPTION:
MILLER CREEK 111.0
END DESCRIPTION:
XS GIS Cut Line= 3
      2861155.69     10283953.11      2861100.00     10283943.00
      2860855.64     10283903.10
#Sta/Elev= 30
  4943.4 1336.47  4945.9 1336.47  4953.6 1333.96  4963.7 1330.13  4968.8 1328.59
  4975.2 1324.78  4982.1 1321.99  4982.3 1321.49  4985.8 1321.49  4986.1 1321.99
  4994.2 1322.35  4999.7 1323.71  5004.7 1323.71  5014.5 1325.07  5024.6 1325.41
  5030.0 1325.85  5035.1 1325.90  5055.0 1325.45  5075.3 1326.42  5085.4 1326.62
  5091.4 1327.00  5096.5 1327.03  5115.8 1327.87  5126.0 1328.13  5136.1 1328.88
  5176.6 1329.99  5207.0 1331.73  5227.3 1331.89  5245.0 1332.92  5247.6 1332.92
#Mann=3,-1,0
  4943.4    0.05       0  4982.1    0.05       0  4986.1    0.05       0
Bank Sta=4982.1,4986.1
Exp/Cntr=0.3,0.1

Type RM Length L Ch R = 1,59452,426,426,426
BEGIN DESCRIPTION:
MILLER CREEK 110.0
END DESCRIPTION:
XS GIS Cut Line= 3
      2861405.66     10283803.08      2861205.00     10283519.00
      2861005.73     10283503.12
#Sta/Elev= 30
  4652.2 1339.41  4655.2 1339.41  4659.6 1338.47  4674.3 1337.03  4680.5 1337.08
  4695.3 1335.01  4710.0 1334.06  4737.9 1333.56  4745.7 1331.93  4766.6 1329.60
  4823.6 1326.33  4873.7 1322.57  4884.0 1322.26  4968.6 1319.34  4974.7 1318.56
  4982.7 1315.99  4993.1 1315.83  4993.3 1315.33  4996.8 1315.33  4997.1 1315.83
  5002.2 1315.83  5007.8 1316.93  5019.4 1318.38  5041.5 1319.65  5089.6 1322.39
  5109.7 1322.67  5135.9 1324.41  5140.9 1324.07  5169.9 1325.75  5199.9 1326.80
#Mann=5,-1,0
  4652.2    0.05       0  4884.0    0.12       0  4993.1    0.07       0
  4997.1    0.12       0  5041.5    0.05       0
Bank Sta=4993.1,4997.1
Exp/Cntr=0.3,0.1

Type RM Length L Ch R = 1,59026,345,345,345
BEGIN DESCRIPTION:
MILLER CREEK 109.0
END DESCRIPTION:
XS GIS Cut Line= 3
      2861505.68     10283353.11      2861313.50     10283110.00
      2861005.70     10283153.11
#Sta/Elev= 30
  4690.1 1322.96  4775.9 1319.31  4831.9 1317.83  4860.8 1316.54  4868.6 1316.75
  4889.7 1316.17  4904.1 1316.73  4924.9 1316.50  4945.7 1314.28  4953.8 1314.02
  4968.2 1312.41  4974.6 1311.01  4987.0 1309.86  4987.3 1309.36  4990.8 1309.36
  4991.0 1309.86  5000.0 1310.20  5018.0 1313.41  5038.2 1313.71  5048.3 1313.41
  5068.5 1314.45  5078.6 1313.55  5088.7 1311.53  5098.8 1311.41  5108.9 1312.81
  5149.3 1315.43  5203.7 1317.61  5230.0 1319.19  5275.1 1320.86  5310.8 1323.21
#Mann=3,-1,0
  4690.1    0.05       0  4987.0    0.03       0  4991.0    0.05       0
Bank Sta=4987,4991
Exp/Cntr=0.3,0.1

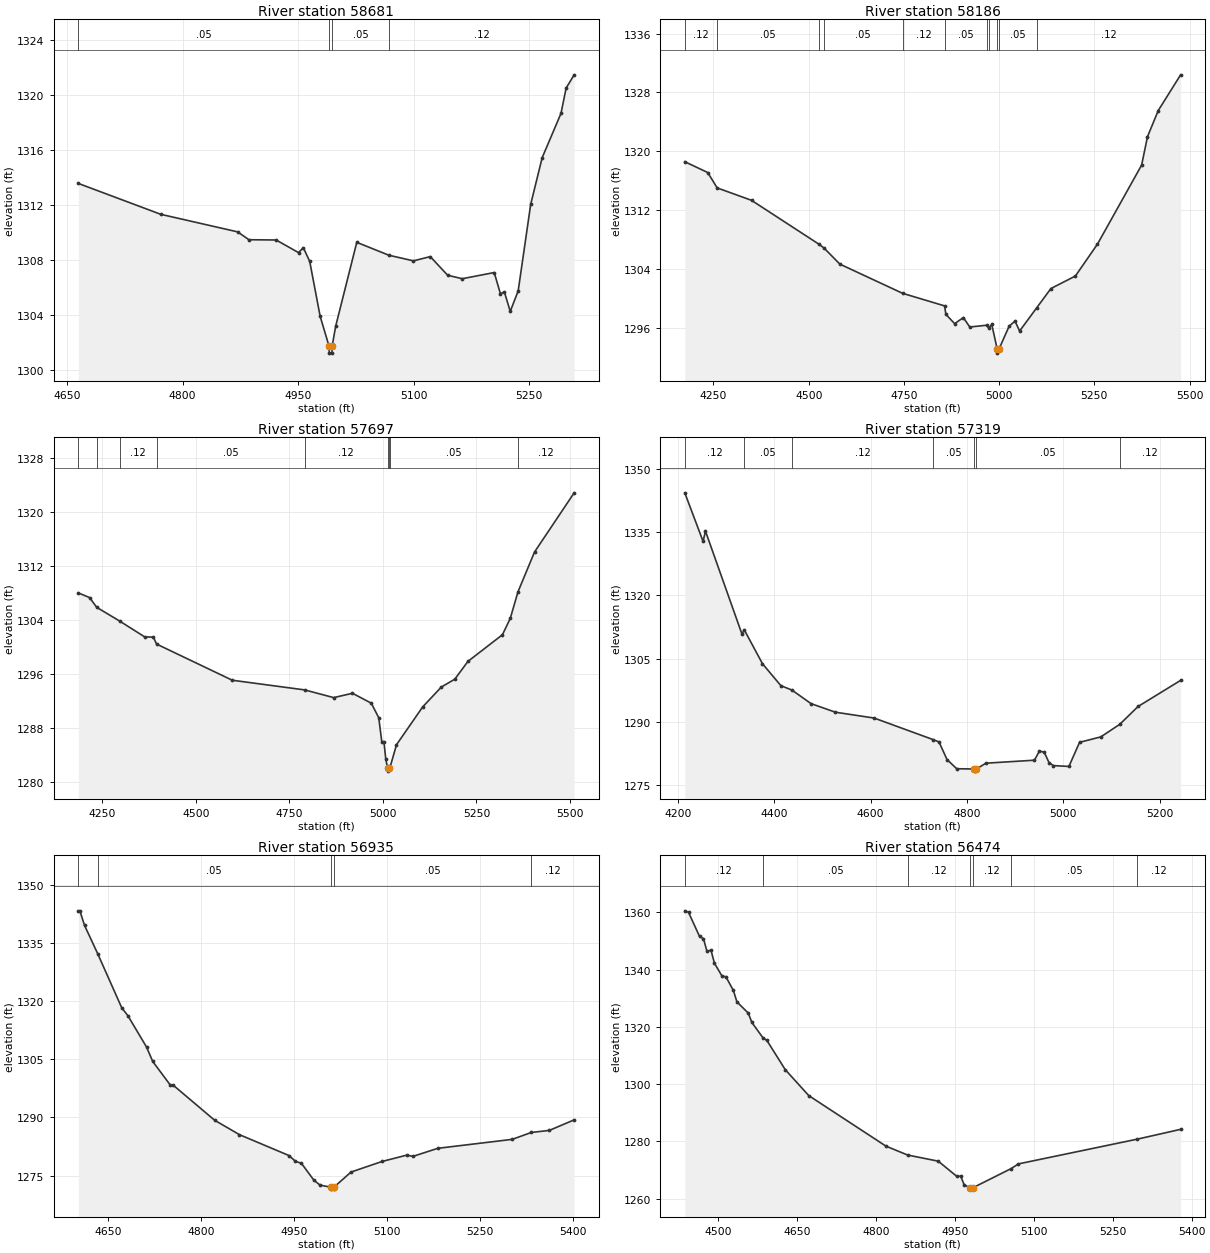
Type RM Length L Ch R = 1,58681,495,495,495
BEGIN DESCRIPTION:
MILLER CREEK 108.0
END DESCRIPTION:
XS GIS Cut Line= 3
      2861605.71     10283053.15      2861402.75     10282786.00
      2861105.70     10282703.12
#Sta/Elev= 30
  4664.5 1313.57  4771.6 1311.32  4871.5 1310.04  4886.0 1309.47  4921.4 1309.45
  4950.5 1308.53  4956.7 1308.89  4965.0 1307.89  4978.5 1303.90  4990.1 1301.71
  4990.4 1301.21  4993.9 1301.21  4994.1 1301.71  4998.7 1303.17  5026.1 1309.28
  5067.8 1308.34  5099.7 1307.93  5121.5 1308.24  5144.2 1306.88  5163.1 1306.63
  5204.6 1307.08  5212.6 1305.54  5217.8 1305.66  5225.4 1304.25  5235.7 1305.74
  5252.0 1312.06  5266.9 1315.45  5291.3 1318.67  5298.0 1320.52  5308.4 1321.48
#Mann=4,-1,0
  4664.5    0.05       0  4990.1    0.05       0  4994.1    0.05       0
  5067.8    0.12       0
Bank Sta=4990.1,4994.1
Exp/Cntr=0.3,0.1

Type RM Length L Ch R = 1,58186,489,489,489
BEGIN DESCRIPTION:
MILLER CREEK 107.0
END DESCRIPTION:
XS GIS Cut Line= 3
      2861855.68     10283103.11      2861511.50     10282353.00
      2861105.67     10282103.10
#Sta/Elev= 30
  4174.7 1318.58  4234.9 1317.11  4259.7 1315.02  4349.9 1313.33  4526.2 1307.39
  4540.2 1306.85  4581.8 1304.66  4746.6 1300.69  4856.9 1298.98  4860.2 1297.83
  4883.2 1296.57  4906.2 1297.39  4922.9 1296.11  4967.1 1296.35  4973.3 1295.95
  4980.7 1296.47  4995.2 1293.06  4995.4 1292.56  4999.2 1293.06  5026.4 1296.23
  5041.8 1296.91  5053.8 1295.56  5099.1 1298.75  5136.0 1301.34  5200.3 1303.04
  5258.3 1307.38  5374.2 1318.12  5389.6 1321.98  5417.9 1325.54  5476.6 1330.39
#Mann=11,-1,0
  4174.7    0.12       0  4259.7    0.05       0  4526.2    0.12       0
  4540.2    0.05       0  4746.6    0.12       0  4856.9    0.05       0
  4967.1    0.12       0  4973.3    0.05       0  4995.2    0.05       0
  4999.2    0.05       0  5099.1    0.12       0
Bank Sta=4995.2,4999.2
Exp/Cntr=0.3,0.1

Type RM Length L Ch R = 1,57697,378,378,378
BEGIN DESCRIPTION:
MILLER CREEK 106.0
END DESCRIPTION:
XS GIS Cut Line= 3
      2861905.68     10282803.12      2861837.25     10281992.00
      2861505.72     10281603.15
#Sta/Elev= 30
  4186.0 1307.98  4216.1 1307.29  4235.1 1305.85  4296.1 1303.83  4363.0 1301.49
  4386.7 1301.44  4395.0 1300.42  4597.4 1295.07  4790.8 1293.64  4868.4 1292.50
  4918.6 1293.14  4968.8 1291.68  4988.8 1289.53  4996.9 1285.98  5002.6 1285.98
  5007.6 1283.42  5012.2 1282.13  5012.4 1281.63  5016.2 1282.13  5019.3 1282.26
  5036.2 1285.53  5106.4 1291.14  5156.2 1294.07  5192.1 1295.23  5227.2 1297.86
  5319.4 1301.80  5340.3 1304.22  5361.0 1308.16  5405.1 1314.03  5511.0 1322.78
#Mann=9,-1,0
  4186.0    0.12       0  4235.1    0.05       0  4296.1    0.12       0
  4395.0    0.05       0  4790.8    0.12       0  5012.2    0.07       0
  5016.2    0.12       0  5019.3    0.05       0  5361.0    0.12       0
Bank Sta=5012.2,5016.2
Exp/Cntr=0.3,0.1

Type RM Length L Ch R = 1,57319,384,384,384
BEGIN DESCRIPTION:
MILLER CREEK 105.0
END DESCRIPTION:
XS GIS Cut Line= 3
      2862855.68     10281803.11      2862076.00     10281706.00
      2861855.64     10281603.09
#Sta/Elev= 30
  4214.3 1344.29  4252.2 1332.79  4257.2 1335.21  4332.9 1310.83  4337.6 1311.86
  4375.5 1303.81  4413.7 1298.61  4436.6 1297.57  4476.3 1294.36  4526.7 1292.33
  4607.3 1290.94  4729.0 1285.86  4741.8 1285.29  4758.5 1281.10  4778.6 1278.94
  4815.4 1278.87  4815.7 1278.37  4819.5 1278.87  4839.1 1280.25  4939.9 1280.96
  4949.9 1283.08  4960.0 1282.90  4970.1 1280.39  4979.0 1279.68  5011.4 1279.48
  5033.5 1285.19  5077.6 1286.48  5116.7 1289.44  5154.9 1293.68  5243.2 1299.87
#Mann=7,-1,0
  4214.3    0.12       0  4337.6    0.05       0  4436.6    0.12       0
  4729.0    0.05       0  4815.4    0.05       0  4819.5    0.05       0
  5116.7    0.12       0
Bank Sta=4815.4,4819.5
Exp/Cntr=0.3,0.1

Type RM Length L Ch R = 1,56935,461,461,461
BEGIN DESCRIPTION:
MILLER CREEK 104.0
END DESCRIPTION:
XS GIS Cut Line= 3
      2862755.68     10281503.11      2862357.50     10281490.00
      2861955.71     10281503.11
#Sta/Elev= 30
  4601.6 1343.23  4604.1 1343.23  4611.6 1339.48  4632.8 1332.20  4671.6 1318.26
  4681.6 1316.19  4711.7 1308.12  4721.7 1304.40  4750.1 1298.31  4755.1 1298.24
  4821.7 1289.24  4861.7 1285.53  4941.8 1280.14  4951.8 1278.68  4961.8 1278.14
  4981.8 1273.80  4991.8 1272.52  5009.4 1271.99  5009.8 1271.49  5013.9 1271.49
  5014.2 1271.99  5041.8 1275.89  5091.9 1278.62  5131.9 1280.26  5141.9 1279.94
  5181.9 1282.01  5302.0 1284.32  5332.9 1286.10  5362.0 1286.63  5402.0 1289.35
#Mann=5,-1,0
  4601.6    0.12       0  4632.8    0.05       0  5009.4    0.05       0
  5014.2    0.05       0  5332.9    0.12       0
Bank Sta=5009.4,5014.2
Exp/Cntr=0.3,0.1

Type RM Length L Ch R = 1,56474,424,424,424
BEGIN DESCRIPTION:
MILLER CREEK 103.0
END DESCRIPTION:
XS GIS Cut Line= 3
      2862805.66     10281453.09      2862428.75     10281035.00
      2862055.72     10281103.11
#Sta/Elev= 30
  4437.1 1360.49  4444.2 1359.98  4465.1 1351.55  4472.6 1350.77  4479.3 1346.30
  4486.8 1346.80  4493.5 1342.16  4507.7 1337.76  4515.2 1337.47  4529.4 1332.69
  4536.1 1328.72  4557.8 1324.77  4564.5 1321.53  4585.9 1316.09  4592.9 1315.30
  4628.0 1305.04  4672.7 1295.98  4819.3 1278.35  4860.5 1275.24  4918.7 1273.10
  4953.9 1267.80  4961.3 1267.87  4968.1 1264.77  4979.8 1263.84  4980.2 1263.34
  4984.7 1263.84  5057.3 1270.52  5071.1 1272.15  5297.2 1280.80  5379.2 1284.21
#Mann=7,-1,0
  4437.1    0.12       0  4585.9    0.05       0  4860.5    0.12       0
  4979.8    0.07       0  4984.7    0.12       0  5057.3    0.05       0
  5297.2    0.12       0
Bank Sta=4979.8,4984.7
Exp/Cntr=0.3,0.1

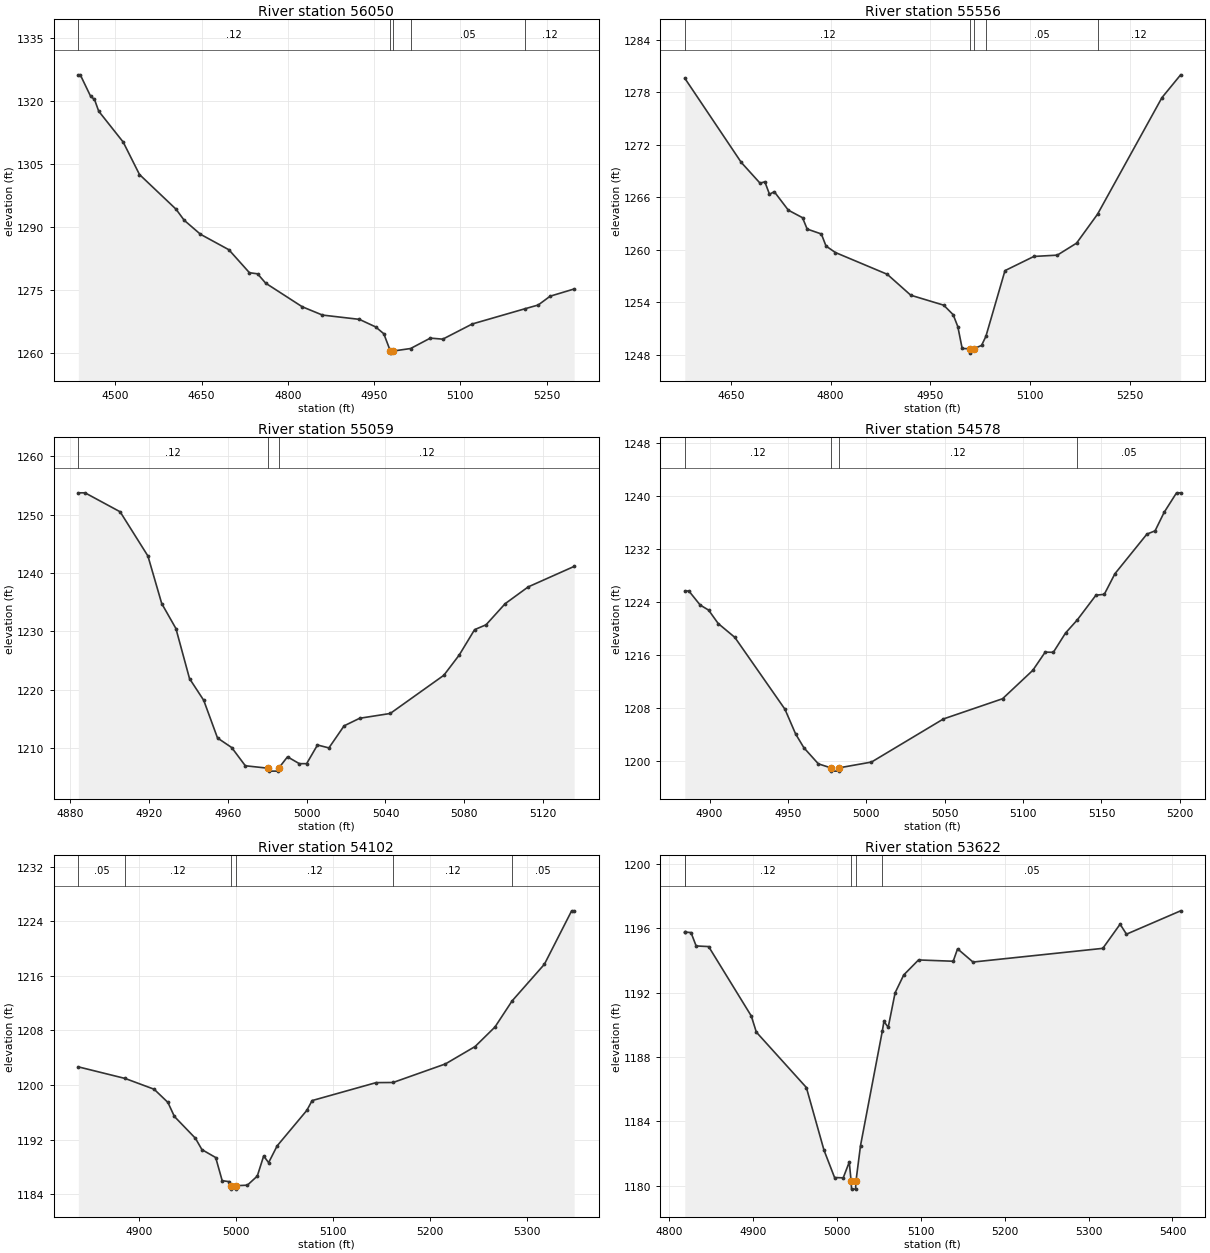
Type RM Length L Ch R = 1,56050,494,494,494
BEGIN DESCRIPTION:
MILLER CREEK 102.0
END DESCRIPTION:
XS GIS Cut Line= 3
      2862905.68     10281003.11      2862491.50     10280620.00
      2862205.64     10280703.12
#Sta/Elev= 30
  4435.8 1326.19  4439.2 1326.19  4457.1 1321.09  4463.9 1320.32  4471.2 1317.53
  4513.8 1310.16  4542.1 1302.43  4605.6 1294.17  4619.8 1291.53  4648.1 1288.19
  4697.5 1284.50  4733.2 1279.03  4747.4 1278.76  4761.5 1276.53  4825.0 1270.91
  4860.2 1268.93  4924.3 1267.91  4952.6 1266.11  4966.8 1264.48  4978.2 1260.36
  4978.6 1259.86  4983.1 1260.36  5013.4 1260.96  5047.7 1263.44  5069.3 1263.19
  5120.6 1266.81  5212.8 1270.46  5235.2 1271.33  5256.0 1273.43  5297.7 1275.15
#Mann=5,-1,0
  4435.8    0.12       0  4978.2    0.07       0  4983.1    0.12       0
  5013.4    0.05       0  5212.8    0.12       0
Bank Sta=4978.2,4983.1
Exp/Cntr=0.3,0.1

Type RM Length L Ch R = 1,55556,497,497,497
BEGIN DESCRIPTION:
MILLER CREEK 101.0
END DESCRIPTION:
XS GIS Cut Line= 3
      2862955.68     10280453.11      2862657.25     10280159.00
      2862455.71     10279903.14
#Sta/Elev= 30
  4581.0 1279.61  4665.8 1269.99  4694.1 1267.61  4701.2 1267.78  4708.2 1266.35
  4715.4 1266.64  4736.5 1264.53  4757.8 1263.67  4764.8 1262.37  4786.1 1261.81
  4793.1 1260.43  4807.2 1259.69  4885.1 1257.20  4920.4 1254.81  4969.9 1253.67
  4984.1 1252.58  4991.1 1251.21  4997.6 1248.72  5009.5 1248.69  5010.0 1248.19
  5014.9 1248.69  5026.7 1249.07  5033.2 1250.10  5061.9 1257.62  5105.3 1259.24
  5140.5 1259.39  5169.4 1260.76  5200.9 1264.07  5297.7 1277.40  5325.7 1280.00
#Mann=5,-1,0
  4581.0    0.12       0  5009.5    0.07       0  5014.9    0.12       0
  5033.2    0.05       0  5200.9    0.12       0
Bank Sta=5009.5,5014.9
Exp/Cntr=0.3,0.1

Type RM Length L Ch R = 1,55059,481,481,481
BEGIN DESCRIPTION:
MILLER CREEK 100.0
END DESCRIPTION:
XS GIS Cut Line= 3
      2863205.65     10280203.08      2863122.00     10280123.00
      2863005.68     10280053.11
#Sta/Elev= 30
  4884.2 1253.72  4887.6 1253.72  4905.4 1250.47  4919.5 1242.89  4926.5 1234.74
  4933.7 1230.46  4940.6 1221.88  4947.8 1218.16  4954.8 1211.70  4962.0 1210.06
  4968.9 1206.94  4980.4 1206.52  4980.8 1206.02  4985.4 1206.02  4985.8 1206.52
  4990.3 1208.47  4996.3 1207.30  5000.0 1207.30  5005.5 1210.50  5011.3 1210.00
  5019.0 1213.78  5026.9 1215.08  5042.4 1215.90  5069.6 1222.45  5077.4 1225.92
  5085.2 1230.27  5091.0 1231.10  5100.7 1234.72  5112.4 1237.60  5135.7 1241.11
#Mann=3,-1,0
  4884.2    0.12       0  4980.4    0.07       0  4985.8    0.12       0
Bank Sta=4980.4,4985.8
Exp/Cntr=0.3,0.1

Type RM Length L Ch R = 1,54578,476,476,476
BEGIN DESCRIPTION:
MILLER CREEK 99.0
END DESCRIPTION:
XS GIS Cut Line= 3
      2863505.64     10279803.09      2863397.00     10279763.00
      2863205.66     10279703.10
#Sta/Elev= 30
  4884.2 1225.64  4886.8 1225.64  4894.0 1223.52  4899.4 1222.75  4905.5 1220.73
  4916.1 1218.64  4948.1 1207.78  4954.9 1204.05  4960.2 1201.96  4969.4 1199.54
  4977.3 1198.94  4977.7 1198.44  4982.3 1198.44  4982.7 1198.94  5003.3 1199.81
  5049.2 1206.32  5086.9 1209.37  5106.2 1213.66  5114.1 1216.41  5119.3 1216.38
  5127.1 1219.30  5134.5 1221.25  5146.5 1225.01  5151.8 1225.13  5158.6 1228.25
  5179.0 1234.23  5184.2 1234.72  5190.0 1237.52  5197.9 1240.46  5200.5 1240.46
#Mann=4,-1,0
  4884.2    0.12       0  4977.3    0.07       0  4982.7    0.12       0
  5134.5    0.05       0
Bank Sta=4977.3,4982.7
Exp/Cntr=0.3,0.1

Type RM Length L Ch R = 1,54102,480,480,480
BEGIN DESCRIPTION:
MILLER CREEK 98.0
END DESCRIPTION:
XS GIS Cut Line= 3
      2863705.71     10279453.14      2863597.25     10279332.00
      2863255.67     10279403.11
#Sta/Elev= 30
  4837.4 1202.66  4885.7 1200.96  4915.6 1199.38  4929.8 1197.45  4936.5 1195.39
  4958.2 1192.19  4964.9 1190.53  4979.1 1189.37  4985.8 1185.98  4993.3 1185.83
  4994.7 1185.24  4995.1 1184.74  4999.7 1184.74  5000.2 1185.24  5011.8 1185.32
  5022.0 1186.65  5028.6 1189.60  5033.7 1188.62  5042.5 1191.08  5073.1 1196.28
  5078.6 1197.72  5144.6 1200.35  5162.1 1200.37  5216.1 1203.09  5246.7 1205.64
  5267.2 1208.50  5284.9 1212.33  5318.2 1217.70  5346.3 1225.53  5348.9 1225.53
#Mann=6,-1,0
  4837.4    0.05       0  4885.7    0.12       0  4994.7    0.03       0
  5000.2    0.12       0  5162.1    0.12       0  5284.9    0.05       0
Bank Sta=4994.7,5000.2
Exp/Cntr=0.3,0.1

Type RM Length L Ch R = 1,53622,482,482,482
BEGIN DESCRIPTION:
MILLER CREEK 97.0
END DESCRIPTION:
XS GIS Cut Line= 3
      2863905.68     10279053.11      2863803.25     10278904.00
      2863405.72     10279003.10
#Sta/Elev= 30
  4819.1 1195.76  4819.6 1195.76  4826.5 1195.73  4832.6 1194.90  4847.5 1194.86
  4898.3 1190.55  4904.3 1189.55  4963.9 1186.11  4984.9 1182.22  4997.5 1180.52
  5007.8 1180.50  5015.0 1181.48  5017.2 1180.30  5017.7 1179.80  5022.5 1179.80
  5023.0 1180.30  5028.4 1182.50  5054.4 1189.62  5056.3 1190.21  5061.4 1189.85
  5069.6 1191.99  5079.9 1193.10  5097.5 1194.03  5138.8 1193.95  5144.0 1194.72
  5162.4 1193.90  5317.0 1194.75  5337.6 1196.25  5345.2 1195.63  5409.7 1197.08
#Mann=5,-1,0
  4819.1    0.05       0  4819.6    0.12       0  5017.2    0.07       0
  5023.0    0.12       0  5054.4    0.05       0
Bank Sta=5017.2,5023
Exp/Cntr=0.3,0.1

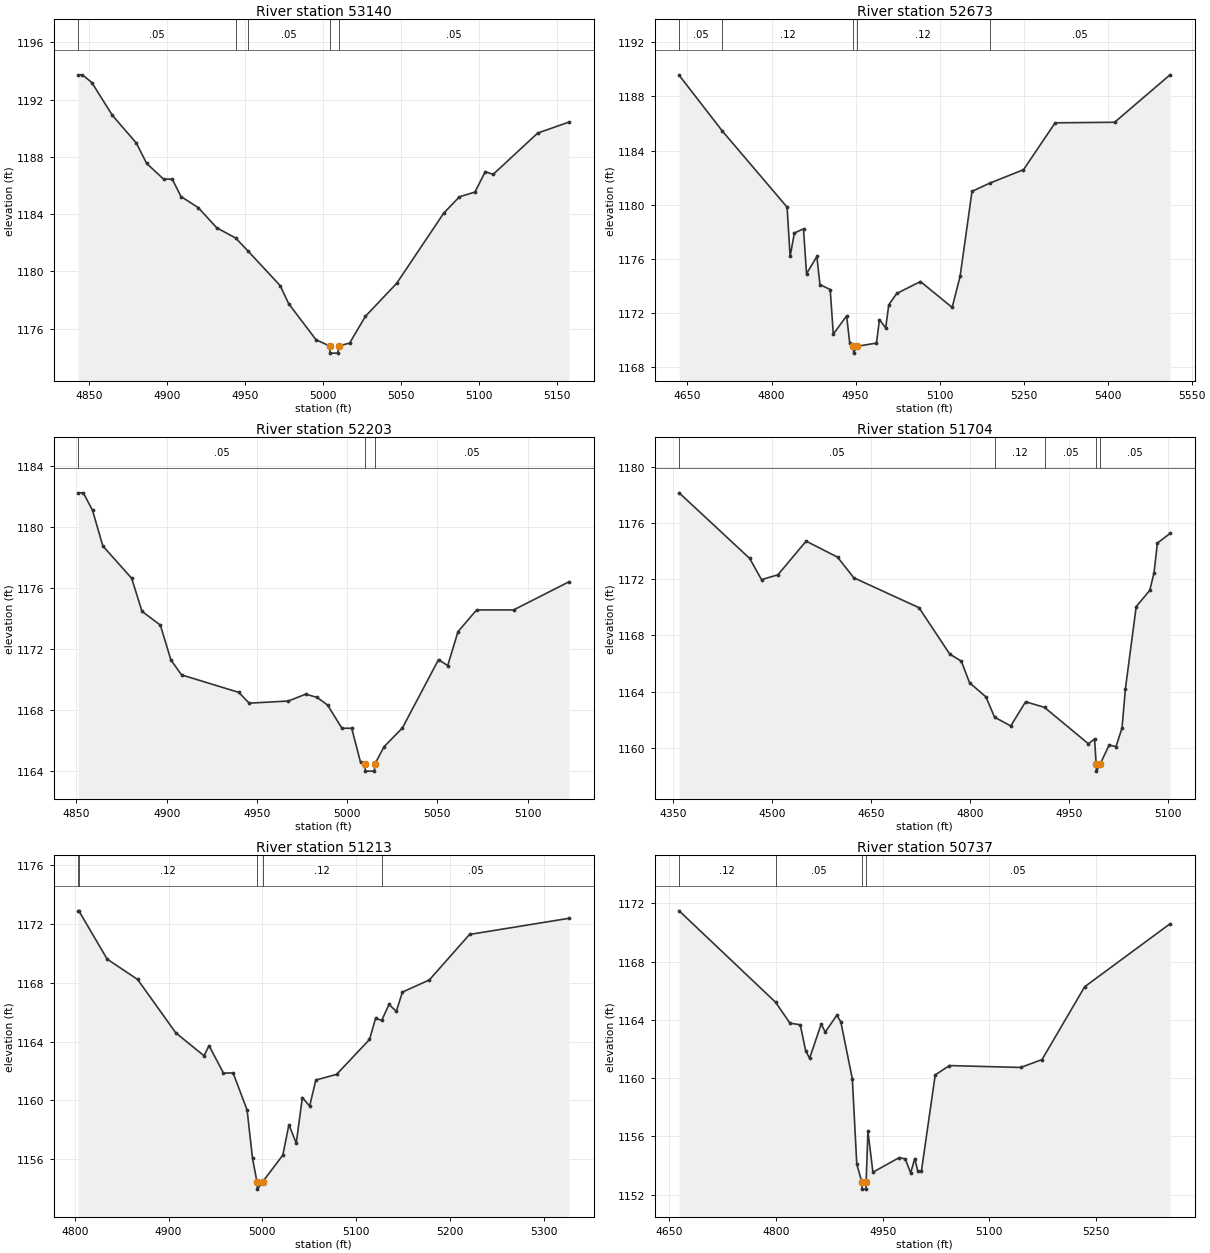
Type RM Length L Ch R = 1,53140,467,467,467
BEGIN DESCRIPTION:
MILLER CREEK 96.0
END DESCRIPTION:
XS GIS Cut Line= 3
      2864255.72     10278603.13      2864112.75     10278538.00
      2863955.68     10278553.11
#Sta/Elev= 30
  4842.9 1193.73  4845.7 1193.73  4851.7 1193.19  4864.9 1190.90  4880.3 1188.96
  4886.9 1187.54  4897.8 1186.44  4903.3 1186.45  4908.9 1185.23  4919.9 1184.46
  4931.9 1183.04  4944.0 1182.33  4952.1 1181.40  4972.5 1179.01  4978.0 1177.74
  4995.5 1175.23  5004.2 1174.79  5004.6 1174.29  5009.5 1174.29  5010.0 1174.79
  5017.1 1174.99  5027.2 1176.86  5047.3 1179.17  5077.4 1184.06  5087.5 1185.21
  5097.5 1185.54  5104.1 1186.97  5109.1 1186.77  5137.7 1189.66  5157.8 1190.43
#Mann=5,-1,0
  4842.9    0.05       0  4944.0    0.12       0  4952.1    0.05       0
  5004.2    0.03       0  5010.0    0.05       0
Bank Sta=5004.2,5010
Exp/Cntr=0.3,0.1

Type RM Length L Ch R = 1,52673,470,470,470
BEGIN DESCRIPTION:
MILLER CREEK 95.0
END DESCRIPTION:
XS GIS Cut Line= 3
      2864355.68     10278453.11      2864216.00     10278116.00
      2863855.67     10277753.10
#Sta/Elev= 30
  4635.1 1189.56  4712.3 1185.44  4827.8 1179.83  4833.2 1176.19  4840.8 1177.92
  4857.1 1178.23  4862.5 1174.92  4881.0 1176.19  4886.4 1174.12  4904.8 1173.75
  4910.3 1170.46  4934.1 1171.81  4939.6 1169.80  4946.1 1169.56  4946.6 1169.06
  4951.9 1169.56  4987.3 1169.80  4992.7 1171.53  5003.8 1170.92  5009.3 1172.62
  5023.5 1173.46  5065.9 1174.34  5122.5 1172.43  5136.6 1174.72  5157.9 1180.99
  5189.6 1181.60  5249.8 1182.59  5306.3 1186.05  5412.4 1186.09  5511.4 1189.59
#Mann=5,-1,0
  4635.1    0.05       0  4712.3    0.12       0  4946.1    0.07       0
  4951.9    0.12       0  5189.6    0.05       0
Bank Sta=4946.1,4951.9
Exp/Cntr=0.3,0.1

Type RM Length L Ch R = 1,52203,499,499,499
BEGIN DESCRIPTION:
MILLER CREEK 94.0
END DESCRIPTION:
XS GIS Cut Line= 3
      2864455.68     10278253.11      2864528.50     10278123.00
      2864555.68     10278003.14
#Sta/Elev= 30
  4850.9 1182.26  4853.8 1182.26  4858.9 1181.11  4864.6 1178.77  4880.6 1176.64
  4886.3 1174.47  4896.5 1173.56  4902.3 1171.28  4908.2 1170.29  4939.9 1169.14
  4945.7 1168.43  4967.4 1168.57  4977.0 1169.02  4983.3 1168.81  4989.1 1168.31
  4997.1 1166.78  5002.5 1166.78  5007.4 1164.54  5009.7 1164.46  5010.1 1163.96
  5015.0 1163.96  5015.5 1164.46  5020.4 1165.56  5030.6 1166.80  5050.6 1171.29
  5055.7 1170.90  5061.4 1173.13  5071.7 1174.56  5092.2 1174.56  5122.9 1176.41
#Mann=3,-1,0
  4850.9    0.05       0  5009.7    0.03       0  5015.5    0.05       0
Bank Sta=5009.7,5015.5
Exp/Cntr=0.3,0.1

Type RM Length L Ch R = 1,51704,491,491,491
BEGIN DESCRIPTION:
MILLER CREEK 93.0
END DESCRIPTION:
XS GIS Cut Line= 3
      2865055.67     10278553.09      2864828.25     10277954.00
      2864805.68     10277853.09
#Sta/Elev= 30
  4359.2 1178.16  4466.1 1173.49  4484.1 1171.98  4508.9 1172.32  4551.7 1174.72
  4599.3 1173.58  4624.0 1172.11  4722.8 1169.98  4769.4 1166.68  4787.0 1166.17
  4799.5 1164.63  4824.3 1163.63  4837.4 1162.18  4861.9 1161.56  4884.5 1163.28
  4913.1 1162.88  4979.6 1160.29  4989.0 1160.63  4991.4 1158.84  4991.9 1158.34
  4997.4 1158.84  5011.2 1160.21  5021.4 1160.08  5030.6 1161.41  5035.7 1164.19
  5052.1 1170.06  5072.6 1171.21  5079.1 1172.45  5084.2 1174.58  5103.4 1175.27
#Mann=5,-1,0
  4359.2    0.05       0  4837.4    0.12       0  4913.1    0.05       0
  4991.4    0.05       0  4997.4    0.05       0
Bank Sta=4991.4,4997.4
Exp/Cntr=0.3,0.1

Type RM Length L Ch R = 1,51213,476,476,476
BEGIN DESCRIPTION:
MILLER CREEK 92.0
END DESCRIPTION:
XS GIS Cut Line= 3
      2865305.69     10278103.14      2865256.50     10277913.00
      2865005.72     10277703.14
#Sta/Elev= 30
  4803.6 1172.91  4804.4 1172.91  4834.6 1169.62  4867.1 1168.23  4907.8 1164.59
  4937.9 1163.03  4943.2 1163.72  4958.6 1161.85  4968.9 1161.86  4983.8 1159.33
  4989.6 1156.03  4994.3 1154.44  4994.8 1153.94  5000.4 1154.44  5021.9 1156.26
  5028.4 1158.33  5036.2 1157.07  5042.7 1160.18  5050.5 1159.60  5057.1 1161.38
  5079.2 1161.76  5114.3 1164.14  5120.8 1165.58  5127.3 1165.44  5135.1 1166.53
  5142.9 1166.06  5149.4 1167.37  5178.1 1168.20  5221.0 1171.30  5327.0 1172.40
#Mann=5,-1,0
  4803.6    0.05       0  4804.4    0.12       0  4994.3    0.07       0
  5000.4    0.12       0  5127.3    0.05       0
Bank Sta=4994.3,5000.4
Exp/Cntr=0.3,0.1

Type RM Length L Ch R = 1,50737,446,446,446
BEGIN DESCRIPTION:
MILLER CREEK 91.0
END DESCRIPTION:
XS GIS Cut Line= 3
      2865805.67     10277853.10      2865509.50     10277694.00
      2865155.72     10277703.11
#Sta/Elev= 30
  4663.8 1171.48  4799.3 1165.21  4819.6 1163.77  4834.1 1163.66  4841.6 1161.89
  4847.2 1161.36  4863.5 1163.71  4869.2 1163.16  4885.4 1164.31  4891.1 1163.86
  4907.3 1159.94  4913.5 1154.11  4920.5 1152.88  4921.0 1152.38  4926.2 1152.38
  4926.7 1152.88  4929.2 1156.36  4936.2 1153.54  4973.1 1154.54  4981.6 1154.46
  4989.3 1153.49  4995.0 1154.48  4999.3 1153.62  5004.4 1153.62  5023.8 1160.22
  5043.8 1160.86  5143.9 1160.73  5173.9 1161.27  5233.9 1166.27  5353.9 1170.59
#Mann=4,-1,0
  4663.8    0.12       0  4799.3    0.05       0  4920.5    0.05       0
  4926.7    0.05       0
Bank Sta=4920.5,4926.7
Exp/Cntr=0.3,0.1