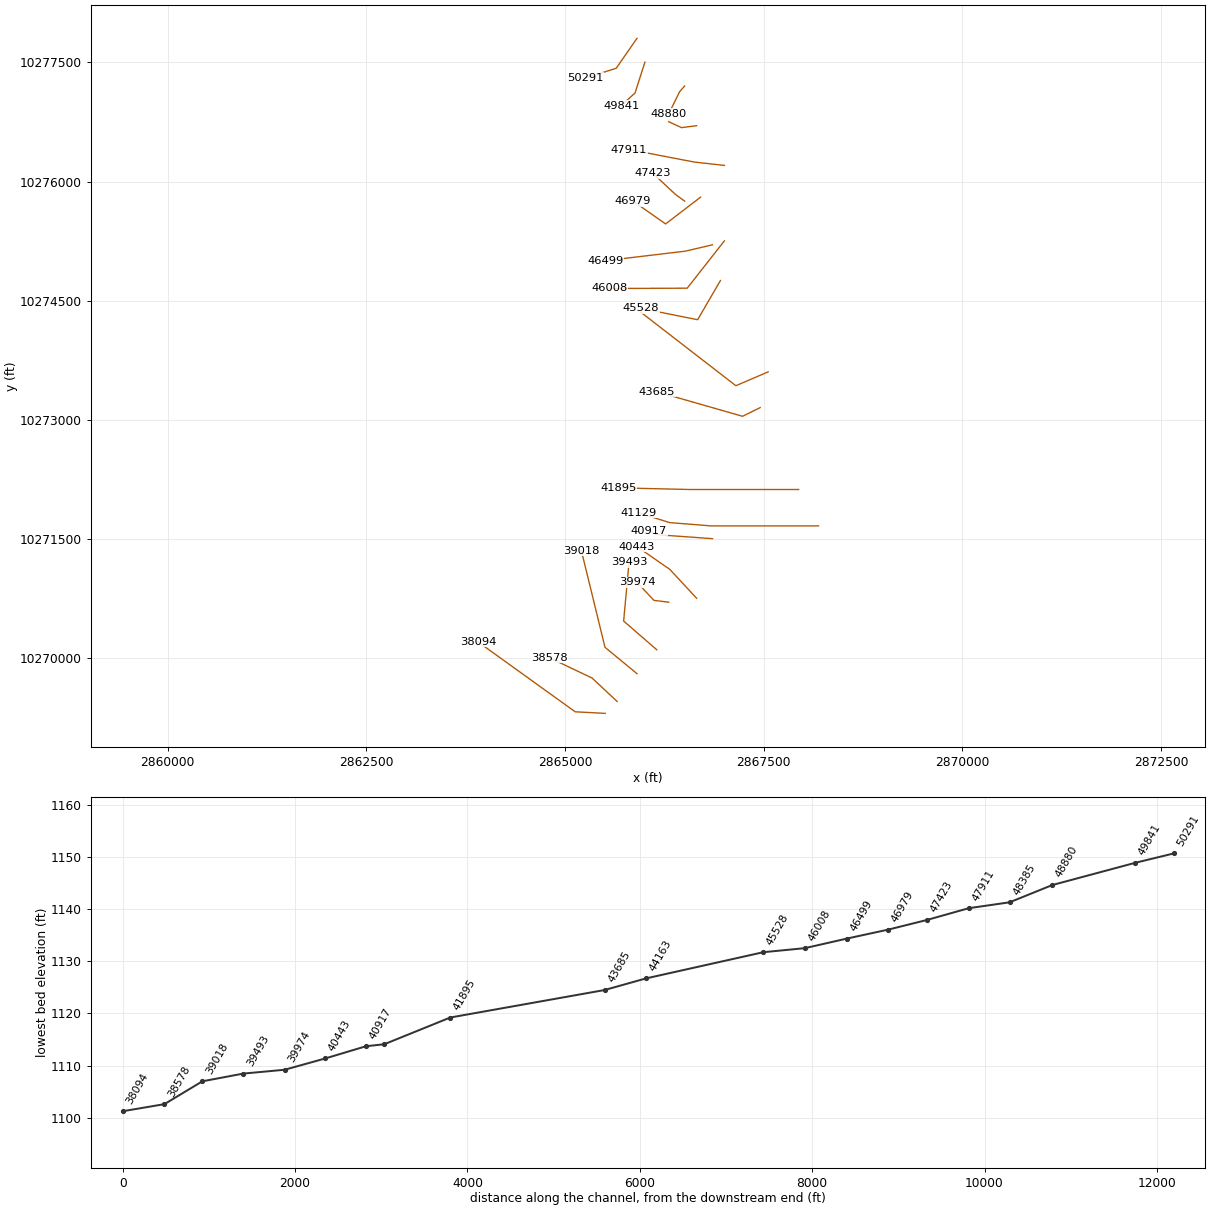
HEC-RAS study MILLER CREEK.prj: MILLER CREEK Base Level Engineering

--- MILLER CREEK.g01 (geometry) --- (continued)

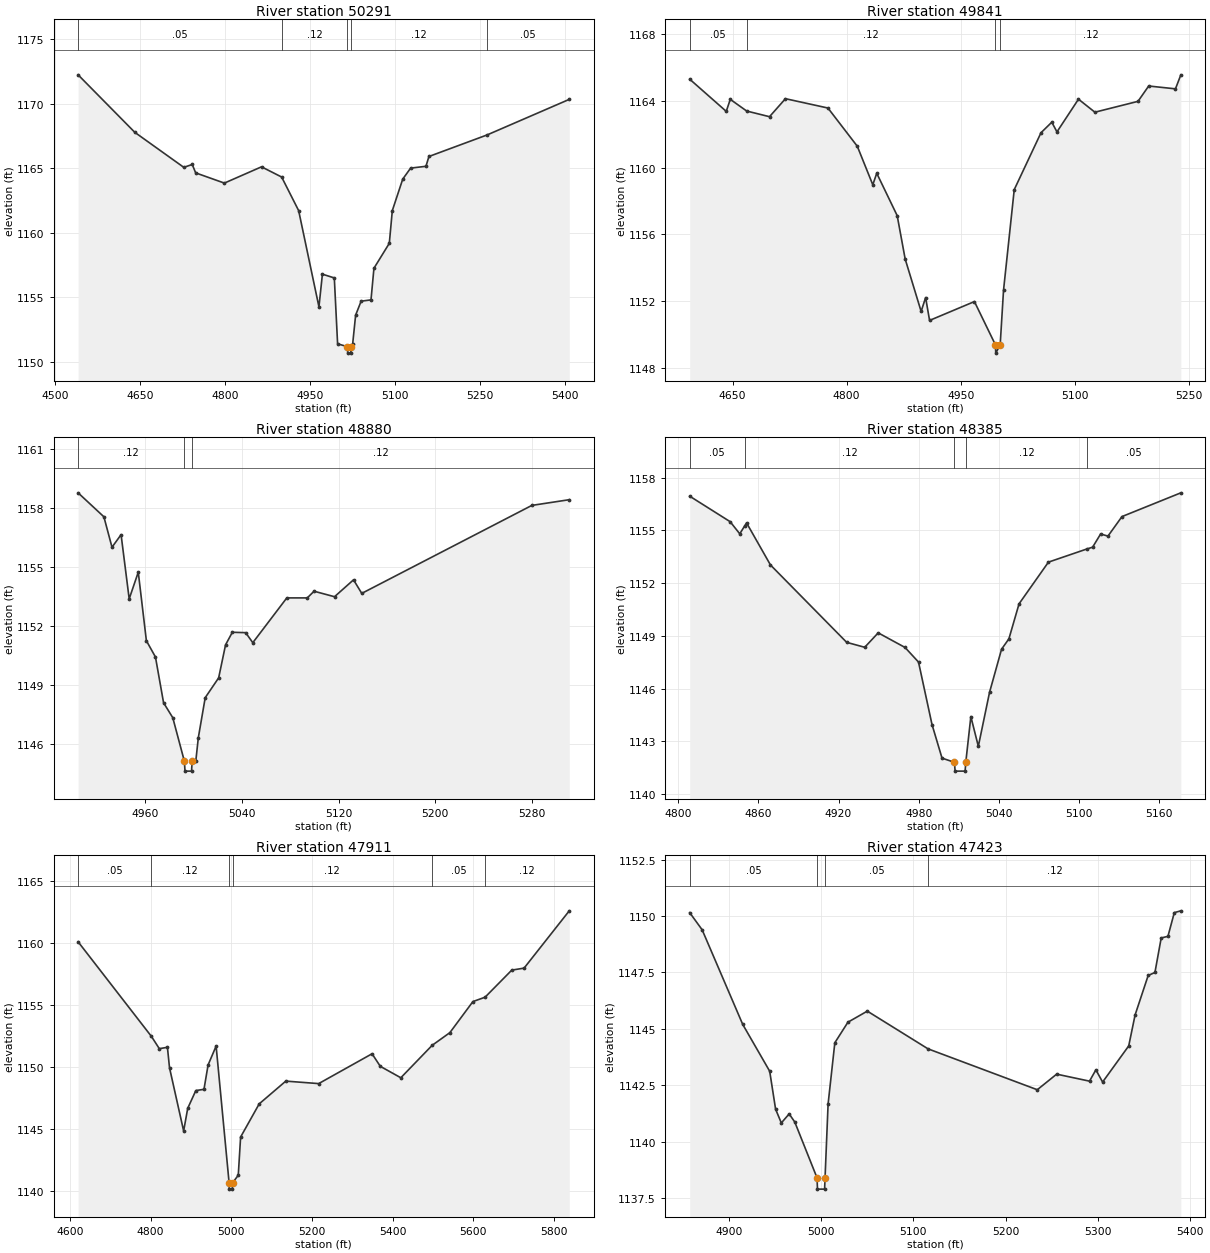
Type RM Length L Ch R = 1,50291,450,450,450
BEGIN DESCRIPTION:
MILLER CREEK 90.0
END DESCRIPTION:
XS GIS Cut Line= 3
      2865905.68     10277803.10      2865644.00     10277426.00
      2865255.68     10277303.11
#Sta/Elev= 30
  4541.0 1172.23  4641.0 1167.78  4727.4 1165.07  4742.3 1165.29  4748.4 1164.64
  4799.0 1163.85  4864.5 1165.11  4900.0 1164.32  4930.0 1161.72  4965.8 1154.27
  4971.9 1156.80  4992.9 1156.51  4998.7 1151.41  5016.1 1151.19  5016.6 1150.69
  5021.9 1150.69  5022.4 1151.19  5025.3 1151.41  5030.5 1153.63  5040.2 1154.71
  5057.6 1154.81  5062.8 1157.26  5089.9 1159.19  5095.2 1161.72  5113.6 1164.16
  5127.5 1165.01  5154.5 1165.15  5159.8 1165.91  5262.5 1167.58  5407.3 1170.33
#Mann=5,-1,0
  4541.0    0.05       0  4900.0    0.12       0  5016.1    0.07       0
  5022.4    0.12       0  5262.5    0.05       0
Bank Sta=5016.1,5022.4
Exp/Cntr=0.3,0.1

Type RM Length L Ch R = 1,49841,961,961,961
BEGIN DESCRIPTION:
MILLER CREEK 89.0
END DESCRIPTION:
XS GIS Cut Line= 3
      2866005.67     10277503.07      2865881.50     10277116.00
      2865705.67     10276953.09
#Sta/Elev= 30
  4593.5 1165.30  4641.6 1163.37  4646.9 1164.09  4668.5 1163.39  4698.5 1163.05
  4719.5 1164.13  4775.4 1163.57  4814.0 1161.28  4834.4 1158.97  4839.6 1159.66
  4866.5 1157.12  4877.0 1154.52  4898.0 1151.38  4903.9 1152.21  4909.1 1150.84
  4968.1 1151.97  4995.7 1149.38  4996.2 1148.88  5002.0 1149.38  5006.4 1152.65
  5020.5 1158.68  5055.7 1162.09  5069.9 1162.72  5076.7 1162.14  5105.0 1164.10
  5126.6 1163.32  5183.3 1163.97  5197.4 1164.89  5232.6 1164.72  5239.7 1165.56
#Mann=4,-1,0
  4593.5    0.05       0  4668.5    0.12       0  4995.7    0.07       0
  5002.0    0.12       0
Bank Sta=4995.7,5002
Exp/Cntr=0.3,0.1

Type RM Length L Ch R = 1,48880,495,495,495
BEGIN DESCRIPTION:
MILLER CREEK 88.0
END DESCRIPTION:
XS GIS Cut Line= 3
      2866505.67     10277203.09      2866442.50     10277132.00
      2866305.70     10276853.15
#Sta/Elev= 30
  4904.9 1158.79  4926.2 1157.57  4932.9 1156.02  4940.4 1156.66  4947.1 1153.39
  4954.6 1154.75  4961.3 1151.26  4968.8 1150.43  4975.5 1148.10  4983.1 1147.34
  4992.7 1145.12  4993.2 1144.62  4998.6 1144.62  4999.1 1145.12  5002.1 1145.12
  5004.2 1146.32  5009.9 1148.36  5021.0 1149.37  5026.7 1151.05  5032.3 1151.69
  5043.3 1151.67  5049.2 1151.16  5077.3 1153.44  5094.2 1153.44  5099.8 1153.78
  5116.7 1153.50  5132.4 1154.36  5139.2 1153.67  5279.7 1158.15  5310.6 1158.44
#Mann=3,-1,0
  4904.9    0.12       0  4992.7    0.07       0  4999.1    0.12       0
Bank Sta=4992.7,4999.1
Exp/Cntr=0.3,0.1

Type RM Length L Ch R = 1,48385,474,474,474
BEGIN DESCRIPTION:
MILLER CREEK 87.0
END DESCRIPTION:
XS GIS Cut Line= 3
      2866655.73     10276703.12      2866465.75     10276679.00
      2866305.68     10276753.12
#Sta/Elev= 30
  4808.5 1156.94  4838.8 1155.49  4846.0 1154.80  4849.7 1155.25  4851.1 1155.42
  4869.0 1153.03  4926.1 1148.63  4939.6 1148.35  4949.7 1149.17  4969.8 1148.34
  4979.9 1147.51  4990.0 1143.96  4997.5 1142.05  5006.8 1141.81  5007.3 1141.31
  5014.8 1141.31  5015.3 1141.81  5019.1 1144.41  5024.7 1142.72  5033.1 1145.79
  5042.1 1148.24  5047.6 1148.83  5055.2 1150.82  5077.2 1153.19  5106.1 1153.94
  5110.3 1154.04  5116.3 1154.79  5121.8 1154.67  5132.3 1155.78  5176.4 1157.13
#Mann=5,-1,0
  4808.5    0.05       0  4849.7    0.12       0  5006.8    0.07       0
  5015.3    0.12       0  5106.1    0.05       0
Bank Sta=5006.8,5015.3
Exp/Cntr=0.3,0.1

Type RM Length L Ch R = 1,47911,488,488,488
BEGIN DESCRIPTION:
MILLER CREEK 86.0
END DESCRIPTION:
XS GIS Cut Line= 3
      2867005.73     10276203.11      2866628.25     10276245.00
      2865805.71     10276403.11
#Sta/Elev= 30
  4620.2 1160.08  4802.1 1152.46  4821.5 1151.48  4841.6 1151.59  4846.8 1149.94
  4881.8 1144.86  4891.9 1146.68  4912.0 1148.11  4932.2 1148.21  4942.4 1150.17
  4962.3 1151.69  4994.5 1140.68  4995.0 1140.18  5002.5 1140.18  5003.0 1140.68
  5017.2 1141.30  5023.0 1144.37  5069.1 1147.04  5135.0 1148.87  5216.5 1148.67
  5348.8 1151.07  5369.2 1150.06  5420.1 1149.14  5497.8 1151.75  5541.7 1152.77
  5598.8 1155.27  5628.9 1155.62  5695.1 1157.80  5725.6 1157.96  5837.6 1162.57
#Mann=6,-1,0
  4620.2    0.05       0  4802.1    0.12       0  4994.5    0.07       0
  5003.0    0.12       0  5497.8    0.05       0  5628.9    0.12       0
Bank Sta=4994.5,5003
Exp/Cntr=0.3,0.1

Type RM Length L Ch R = 1,47423,444,444,444
BEGIN DESCRIPTION:
MILLER CREEK 85.0
END DESCRIPTION:
XS GIS Cut Line= 3
      2866505.69     10275753.11      2866390.75     10275837.00
      2866105.66     10276103.13
#Sta/Elev= 30
  4857.7 1150.15  4871.2 1149.39  4915.2 1145.20  4944.4 1143.13  4950.8 1141.45
  4957.0 1140.84  4965.5 1141.24  4971.6 1140.88  4995.7 1138.41  4996.2 1137.91
  5003.9 1137.91  5004.4 1138.41  5007.7 1141.68  5015.0 1144.39  5029.2 1145.30
  5050.2 1145.79  5116.0 1144.12  5234.4 1142.31  5255.4 1143.00  5291.0 1142.69
  5297.9 1143.19  5305.2 1142.65  5333.5 1144.25  5340.4 1145.62  5354.6 1147.37
  5361.9 1147.50  5368.7 1149.03  5376.0 1149.10  5382.9 1150.15  5390.0 1150.23
#Mann=4,-1,0
  4857.7    0.05       0  4995.7    0.05       0  5004.4    0.05       0
  5116.0    0.12       0
Bank Sta=4995.7,5004.4
Exp/Cntr=0.3,0.1

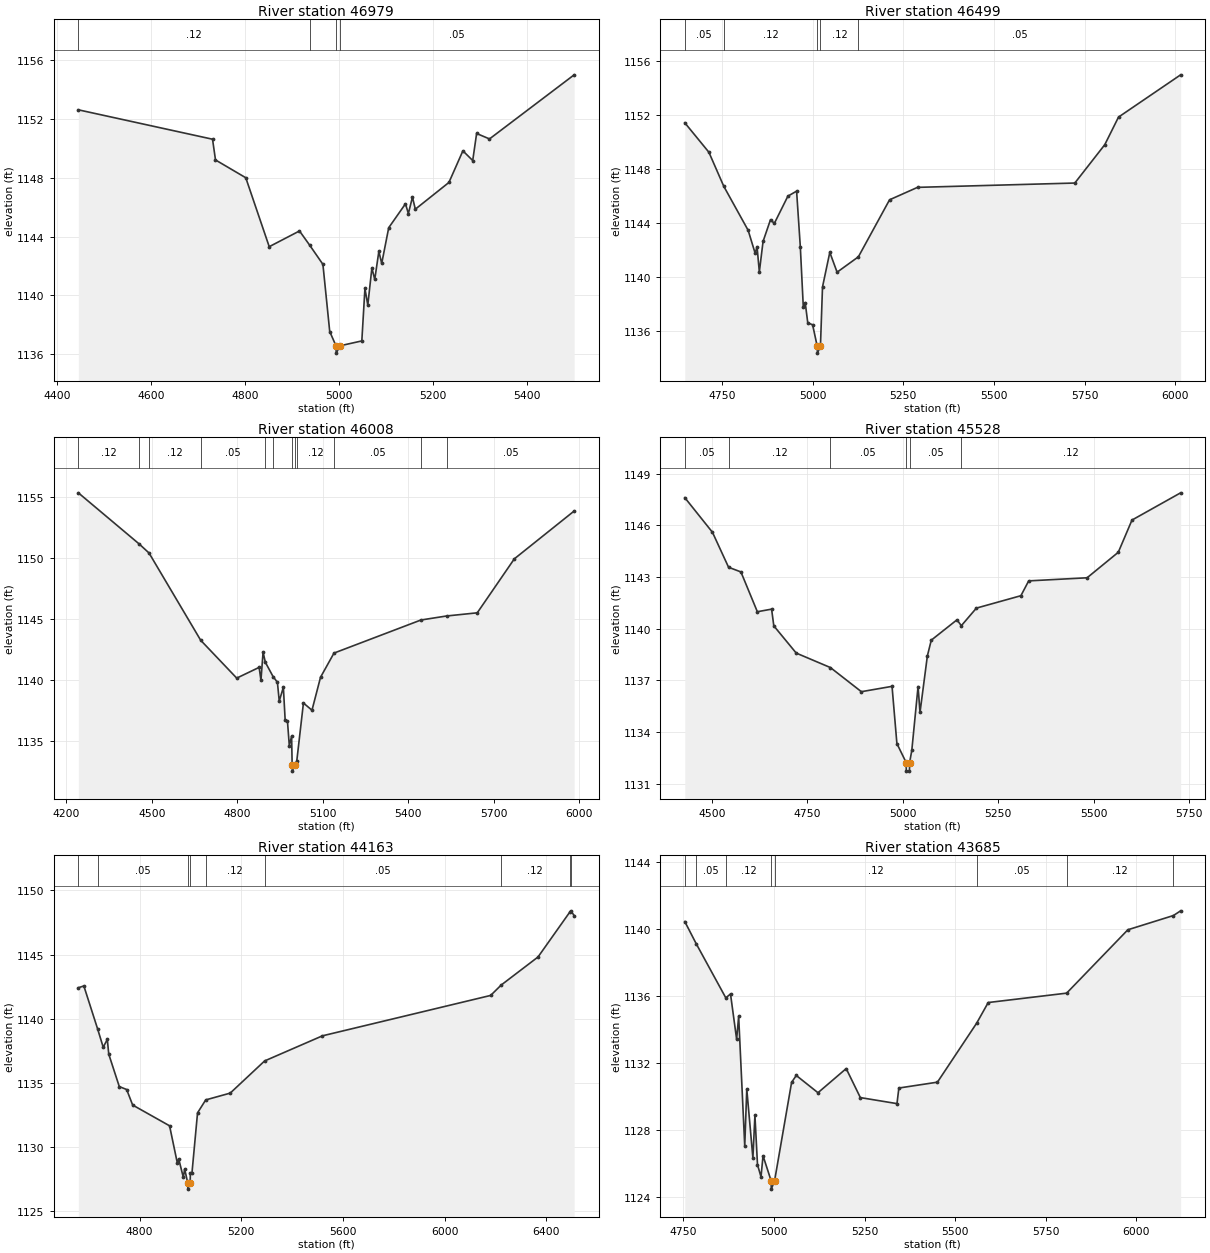
Type RM Length L Ch R = 1,46979,480,480,480
BEGIN DESCRIPTION:
MILLER CREEK 84.0
END DESCRIPTION:
XS GIS Cut Line= 3
      2866705.65     10275803.08      2866265.75     10275466.00
      2865855.67     10275753.12
#Sta/Elev= 30
  4445.8 1152.63  4731.3 1150.63  4737.6 1149.22  4802.0 1148.01  4851.9 1143.32
  4916.3 1144.39  4938.0 1143.42  4966.1 1142.12  4980.6 1137.55  4993.9 1136.58
  4994.4 1136.08  5002.6 1136.58  5048.9 1136.91  5055.5 1140.48  5061.6 1139.35
  5070.3 1141.87  5076.4 1141.09  5085.1 1143.00  5091.2 1142.18  5106.1 1144.61
  5141.8 1146.24  5147.9 1145.57  5156.6 1146.69  5162.7 1145.87  5234.2 1147.69
  5263.9 1149.84  5284.8 1149.18  5293.1 1151.02  5320.5 1150.65  5500.6 1155.01
#Mann=4,-1,0
  4445.8    0.12       0  4938.0    0.05       0  4993.9    0.05       0
  5002.6    0.05       0
Bank Sta=4993.9,5002.6
Exp/Cntr=0.3,0.1

Type RM Length L Ch R = 1,46499,491,491,491
BEGIN DESCRIPTION:
MILLER CREEK 83.0
END DESCRIPTION:
XS GIS Cut Line= 3
      2866855.72     10275203.12      2866512.75     10275123.00
      2865505.66     10275003.11
#Sta/Elev= 30
  4647.8 1151.41  4714.2 1149.23  4755.2 1146.71  4822.4 1143.45  4841.7 1141.75
  4846.9 1142.24  4853.2 1140.37  4863.5 1142.63  4884.0 1144.24  4894.5 1143.96
  4931.9 1145.98  4955.9 1146.35  4966.2 1142.21  4974.4 1137.76  4979.6 1138.10
  4986.7 1136.60  5000.0 1136.46  5012.8 1134.86  5013.3 1134.36  5021.6 1134.86
  5027.3 1139.26  5047.4 1141.82  5067.5 1140.35  5126.2 1141.49  5212.1 1145.71
  5289.1 1146.63  5722.6 1146.95  5805.2 1149.79  5843.0 1151.83  6014.2 1154.96
#Mann=5,-1,0
  4647.8    0.05       0  4755.2    0.12       0  5012.8    0.07       0
  5021.6    0.12       0  5126.2    0.05       0
Bank Sta=5012.8,5021.6
Exp/Cntr=0.3,0.1

Type RM Length L Ch R = 1,46008,480,480,480
BEGIN DESCRIPTION:
MILLER CREEK 82.0
END DESCRIPTION:
XS GIS Cut Line= 3
      2867005.66     10275253.09      2866537.75     10274657.00
      2865555.66     10274653.11
#Sta/Elev= 30
  4242.2 1155.31  4455.7 1151.12  4490.3 1150.38  4671.6 1143.23  4798.0 1140.13
  4876.7 1141.01  4883.0 1139.95  4890.5 1142.26  4898.4 1141.43  4925.7 1140.25
  4940.8 1139.79  4947.2 1138.25  4961.7 1139.38  4968.0 1136.68  4976.1 1136.60
  4982.5 1134.60  4990.6 1135.37  4992.5 1133.01  4993.0 1132.51  5001.3 1133.01
  5008.8 1133.35  5032.1 1138.09  5062.1 1137.50  5092.1 1140.20  5139.3 1142.18
  5444.3 1144.89  5534.4 1145.22  5642.1 1145.48  5772.1 1149.90  5982.1 1153.82
#Mann=12,-1,0
  4242.2    0.12       0  4455.7    0.05       0  4490.3    0.12       0
  4671.6    0.05       0  4898.4    0.12       0  4925.7    0.05       0
  4992.5    0.05       0  5001.3    0.05       0  5008.8    0.12       0
  5139.3    0.05       0  5444.3    0.12       0  5534.4    0.05       0
Bank Sta=4992.5,5001.3
Exp/Cntr=0.3,0.1

Type RM Length L Ch R = 1,45528,1365,1365,1365
BEGIN DESCRIPTION:
MILLER CREEK 81.0
END DESCRIPTION:
XS GIS Cut Line= 3
      2866955.69     10274753.12      2866669.00     10274260.00
      2865955.71     10274403.11
#Sta/Elev= 30
  4429.6 1147.61  4502.0 1145.60  4544.2 1143.57  4576.5 1143.30  4619.5 1140.99
  4656.8 1141.14  4662.6 1140.17  4721.3 1138.59  4810.8 1137.75  4891.8 1136.35
  4972.1 1136.66  4984.8 1133.34  5009.0 1132.24  5009.5 1131.74  5017.6 1131.74
  5018.1 1132.24  5023.8 1132.94  5040.2 1136.65  5045.3 1135.15  5064.6 1138.43
  5074.8 1139.34  5142.0 1140.52  5153.5 1140.18  5192.9 1141.20  5309.4 1141.92
  5329.8 1142.78  5482.7 1142.96  5564.3 1144.44  5600.2 1146.31  5727.5 1147.89
#Mann=6,-1,0
  4429.6    0.05       0  4544.2    0.12       0  4810.8    0.05       0
  5009.0    0.05       0  5018.1    0.05       0  5153.5    0.12       0
Bank Sta=5009,5018.1
Exp/Cntr=0.3,0.1

Type RM Length L Ch R = 1,44163,478,478,478
BEGIN DESCRIPTION:
MILLER CREEK 80.0
END DESCRIPTION:
XS GIS Cut Line= 3
      2867555.65     10273603.10      2867150.25     10273429.00
      2865955.67     10274353.12
#Sta/Elev= 30
  4558.8 1142.41  4580.5 1142.55  4634.5 1139.21  4656.7 1137.77  4672.9 1138.38
  4678.5 1137.23  4720.0 1134.70  4749.0 1134.47  4772.6 1133.26  4917.9 1131.64
  4948.3 1128.75  4953.8 1129.06  4971.9 1127.63  4977.3 1128.26  4989.3 1127.20
  4989.8 1126.70  4998.9 1127.20  4999.8 1127.95  5006.0 1127.95  5028.0 1132.65
  5060.2 1133.66  5156.6 1134.19  5292.0 1136.70  5519.7 1138.66  6181.6 1141.81
  6223.1 1142.62  6368.1 1144.81  6492.0 1148.28  6497.3 1148.41  6510.3 1148.04
#Mann=9,-1,0
  4558.8    0.12       0  4634.5    0.05       0  4989.3    0.05       0
  4998.9    0.05       0  5060.2    0.12       0  5292.0    0.05       0
  6223.1    0.12       0  6492.0    0.05       0  6497.3    0.12       0
Bank Sta=4989.3,4998.9
Exp/Cntr=0.3,0.1

Type RM Length L Ch R = 1,43685,1790,1790,1790
BEGIN DESCRIPTION:
MILLER CREEK 79.0
END DESCRIPTION:
XS GIS Cut Line= 3
      2867455.68     10273153.11      2867234.75     10273044.00
      2866155.65     10273353.12
#Sta/Elev= 30
  4753.6 1140.44  4784.8 1139.13  4866.8 1135.89  4879.8 1136.12  4896.7 1133.42
  4902.3 1134.79  4919.1 1127.04  4924.7 1130.45  4941.6 1126.34  4947.2 1128.88
  4954.3 1125.94  4964.0 1125.21  4969.6 1126.47  4991.9 1124.98  4992.4 1124.48
  5001.5 1124.98  5048.5 1130.85  5061.4 1131.26  5121.3 1130.23  5199.2 1131.67
  5238.3 1129.94  5339.4 1129.58  5344.6 1130.51  5451.1 1130.86  5559.4 1134.38
  5591.3 1135.61  5807.8 1136.17  5976.8 1139.95  6102.7 1140.80  6122.5 1141.08
#Mann=8,-1,0
  4753.6    0.12       0  4784.8    0.05       0  4866.8    0.12       0
  4991.9    0.07       0  5001.5    0.12       0  5559.4    0.05       0
  5807.8    0.12       0  6102.7    0.05       0
Bank Sta=4991.9,5001.5
Exp/Cntr=0.3,0.1

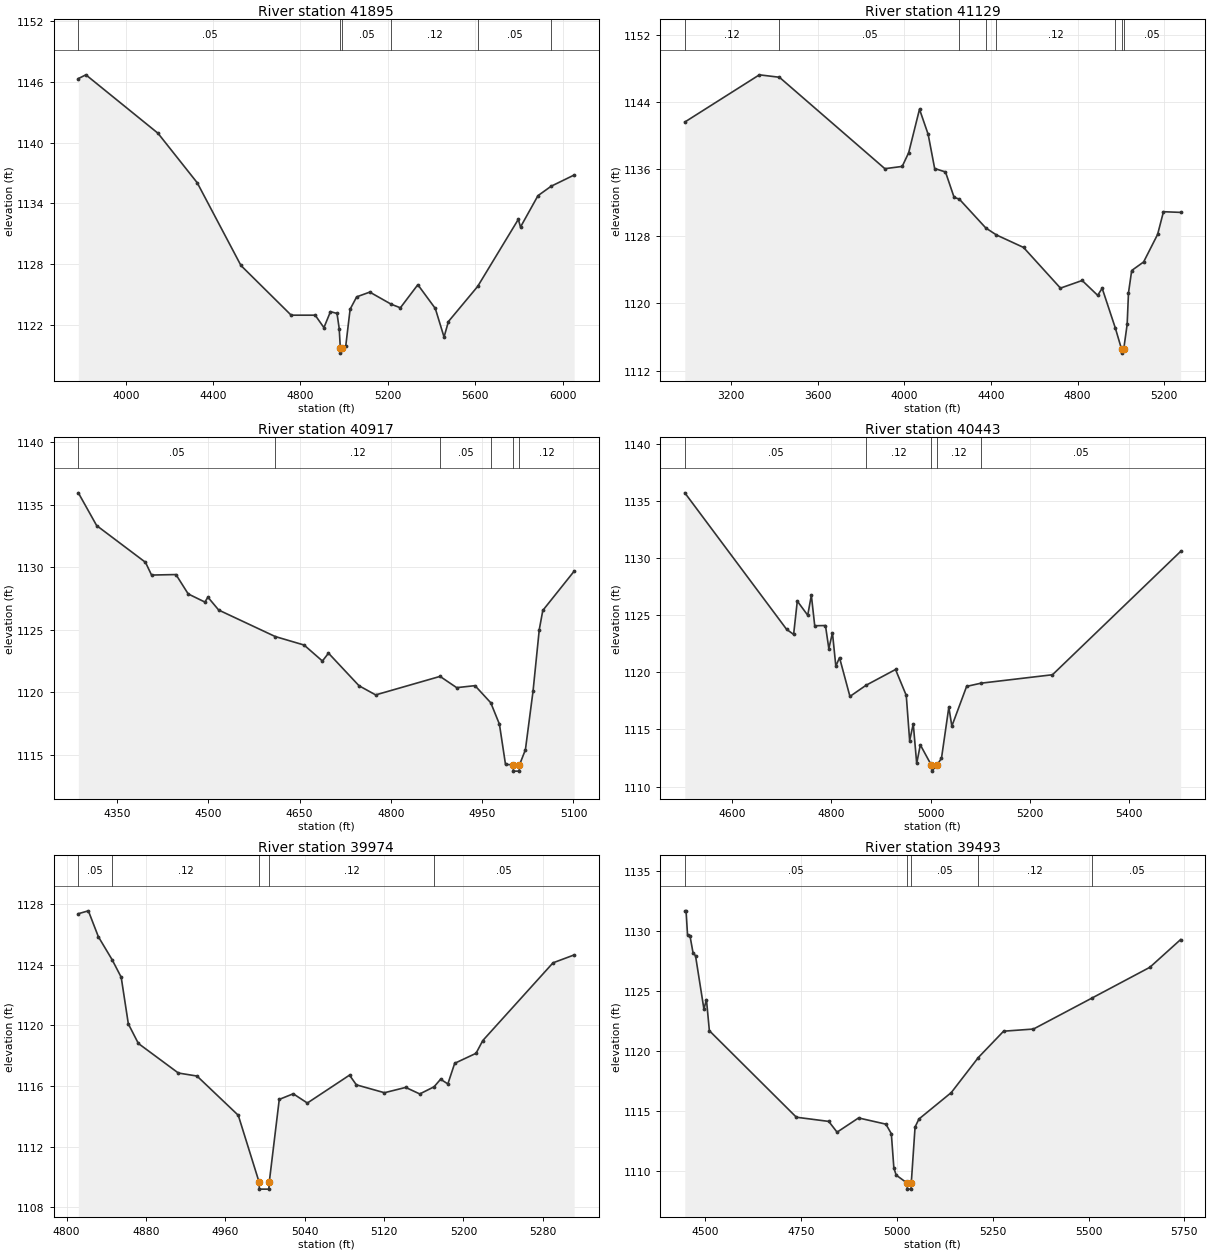
Type RM Length L Ch R = 1,41895,766,766,766
BEGIN DESCRIPTION:
Mapping XS 2cdccd61
END DESCRIPTION:
XS GIS Cut Line= 3
      2867940.31     10272122.23      2866565.31     10272122.23
      2865670.05     10272143.05
#Sta/Elev= 30
  3782.8 1146.34  3817.4 1146.71  4147.4 1140.94  4327.4 1136.04  4527.4 1127.87
  4757.4 1122.96  4867.4 1122.96  4907.4 1121.73  4937.4 1123.31  4967.4 1123.13
  4977.4 1121.64  4982.5 1119.71  4983.0 1119.21  4992.4 1119.71  5007.4 1119.92
  5027.4 1123.55  5057.4 1124.77  5117.4 1125.24  5215.8 1124.04  5257.5 1123.69
  5337.5 1125.97  5417.5 1123.62  5457.5 1120.80  5477.5 1122.33  5611.4 1125.80
  5797.6 1132.43  5807.6 1131.67  5887.6 1134.77  5947.8 1135.70  6053.3 1136.81
#Mann=6,-1,0
  3782.8    0.05       0  4982.5    0.03       0  4992.4    0.05       0
  5215.8    0.12       0  5611.4    0.05       0  5947.8    0.12       0
Bank Sta=4982.5,4992.4
Exp/Cntr=0.3,0.1

Type RM Length L Ch R = 1,41129,212,212,212
BEGIN DESCRIPTION:
Mapping XS 3c1f6463
END DESCRIPTION:
XS GIS Cut Line= 4
      2868190.33     10271663.89      2866836.14     10271663.89
      2866315.31     10271705.56      2865920.03     10271830.38
#Sta/Elev= 30
  2984.9 1141.63  3329.5 1147.26  3422.1 1146.97  3909.5 1136.07  3989.5 1136.34
  4019.5 1137.98  4069.5 1143.16  4109.5 1140.16  4139.5 1136.09  4189.5 1135.68
  4229.5 1132.64  4253.1 1132.45  4375.9 1129.00  4425.0 1128.17  4550.2 1126.68
  4720.8 1121.83  4821.1 1122.74  4892.7 1120.97  4913.6 1121.81  4973.9 1117.11
  5002.9 1114.58  5003.4 1114.08  5013.3 1114.58  5029.0 1117.50  5035.2 1121.27
  5050.0 1123.93  5105.1 1124.95  5169.7 1128.23  5196.8 1130.94  5276.1 1130.86
#Mann=8,-1,0
  2984.9    0.12       0  3422.1    0.05       0  4253.1    0.12       0
  4375.9    0.05       0  4425.0    0.12       0  4973.9    0.05       0
  5002.9    0.05       0  5013.3    0.05       0
Bank Sta=5002.9,5013.3
Exp/Cntr=0.3,0.1

Type RM Length L Ch R = 1,40917,474,474,474
BEGIN DESCRIPTION:
MILLER CREEK 74.0
END DESCRIPTION:
XS GIS Cut Line= 3
      2866855.68     10271503.11      2866144.00     10271554.00
      2866055.64     10271603.13
#Sta/Elev= 30
  4286.5 1135.97  4316.6 1133.35  4396.8 1130.41  4406.8 1129.39  4446.9 1129.43
  4467.0 1127.88  4494.4 1127.23  4499.4 1127.62  4517.1 1126.59  4610.0 1124.47
  4657.4 1123.79  4687.5 1122.51  4697.5 1123.14  4747.7 1120.53  4775.0 1119.80
  4880.8 1121.28  4908.1 1120.38  4938.2 1120.54  4964.1 1119.17  4978.3 1117.46
  4988.3 1114.24  5000.9 1114.20  5001.4 1113.70  5010.8 1113.70  5011.3 1114.20
  5021.0 1115.41  5033.6 1120.12  5043.8 1125.03  5049.6 1126.56  5101.1 1129.70
#Mann=6,-1,0
  4286.5    0.05       0  4610.0    0.12       0  4880.8    0.05       0
  4964.1    0.12       0  5000.9    0.07       0  5011.3    0.12       0
Bank Sta=5000.9,5011.3
Exp/Cntr=0.3,0.1

Type RM Length L Ch R = 1,40443,469,469,469
BEGIN DESCRIPTION:
MILLER CREEK 73.0
END DESCRIPTION:
XS GIS Cut Line= 3
      2866655.67     10270753.13      2866319.00     10271116.00
      2865905.65     10271403.14
#Sta/Elev= 30
  4505.0 1135.72  4709.9 1123.77  4724.1 1123.32  4731.5 1126.24  4752.5 1125.00
  4759.8 1126.75  4766.6 1124.08  4788.2 1124.10  4795.0 1122.08  4802.3 1123.46
  4809.1 1120.54  4816.5 1121.29  4837.5 1117.89  4870.0 1118.87  4929.3 1120.25
  4950.9 1117.98  4957.7 1114.02  4965.0 1115.49  4971.9 1112.02  4979.2 1113.65
  5001.7 1111.85  5002.2 1111.35  5012.1 1111.85  5021.8 1112.47  5036.6 1116.95
  5042.7 1115.29  5072.4 1118.77  5101.3 1119.05  5245.3 1119.79  5503.3 1130.59
#Mann=5,-1,0
  4505.0    0.05       0  4870.0    0.12       0  5001.7    0.07       0
  5012.1    0.12       0  5101.3    0.05       0
Bank Sta=5001.7,5012.1
Exp/Cntr=0.3,0.1

Type RM Length L Ch R = 1,39974,481,481,481
BEGIN DESCRIPTION:
MILLER CREEK 72.0
END DESCRIPTION:
XS GIS Cut Line= 3
      2866305.70     10270703.11      2866119.00     10270726.00
      2865905.67     10270953.12
#Sta/Elev= 30
  4811.9 1127.36  4822.0 1127.55  4832.1 1125.84  4846.0 1124.32  4855.1 1123.17
  4862.3 1120.09  4872.4 1118.80  4912.7 1116.85  4931.5 1116.65  4973.1 1114.06
  4993.9 1109.69  4994.4 1109.19  5003.9 1109.19  5004.4 1109.69  5014.4 1115.11
  5028.5 1115.48  5042.7 1114.87  5085.2 1116.71  5092.1 1116.07  5120.4 1115.55
  5141.8 1115.90  5156.0 1115.47  5170.4 1115.94  5177.0 1116.44  5184.3 1116.13
  5191.2 1117.49  5212.7 1118.15  5219.5 1118.99  5290.3 1124.12  5311.6 1124.64
#Mann=5,-1,0
  4811.9    0.05       0  4846.0    0.12       0  4993.9    0.07       0
  5004.4    0.12       0  5170.4    0.05       0
Bank Sta=4993.9,5004.4
Exp/Cntr=0.3,0.1

Type RM Length L Ch R = 1,39493,475,475,475
BEGIN DESCRIPTION:
MILLER CREEK 71.0
END DESCRIPTION:
XS GIS Cut Line= 3
      2866155.69     10270103.11      2865737.75     10270466.00
      2865805.68     10271203.08
#Sta/Elev= 30
  4446.5 1131.71  4449.8 1131.71  4453.6 1129.71  4460.3 1129.57  4467.9 1128.22
  4474.5 1127.95  4496.4 1123.50  4503.0 1124.29  4510.6 1121.69  4737.6 1114.46
  4822.1 1114.11  4843.8 1113.21  4899.9 1114.40  4971.2 1113.88  4985.4 1113.08
  4992.0 1110.21  4998.1 1109.62  5026.8 1108.95  5027.3 1108.45  5036.9 1108.45
  5037.4 1108.95  5047.3 1113.64  5057.4 1114.31  5141.8 1116.52  5212.4 1119.45
  5278.3 1121.65  5356.2 1121.83  5509.5 1124.43  5659.9 1126.99  5740.2 1129.31
#Mann=5,-1,0
  4446.5    0.05       0  5026.8    0.05       0  5037.4    0.05       0
  5212.4    0.12       0  5509.5    0.05       0
Bank Sta=5026.8,5037.4
Exp/Cntr=0.3,0.1

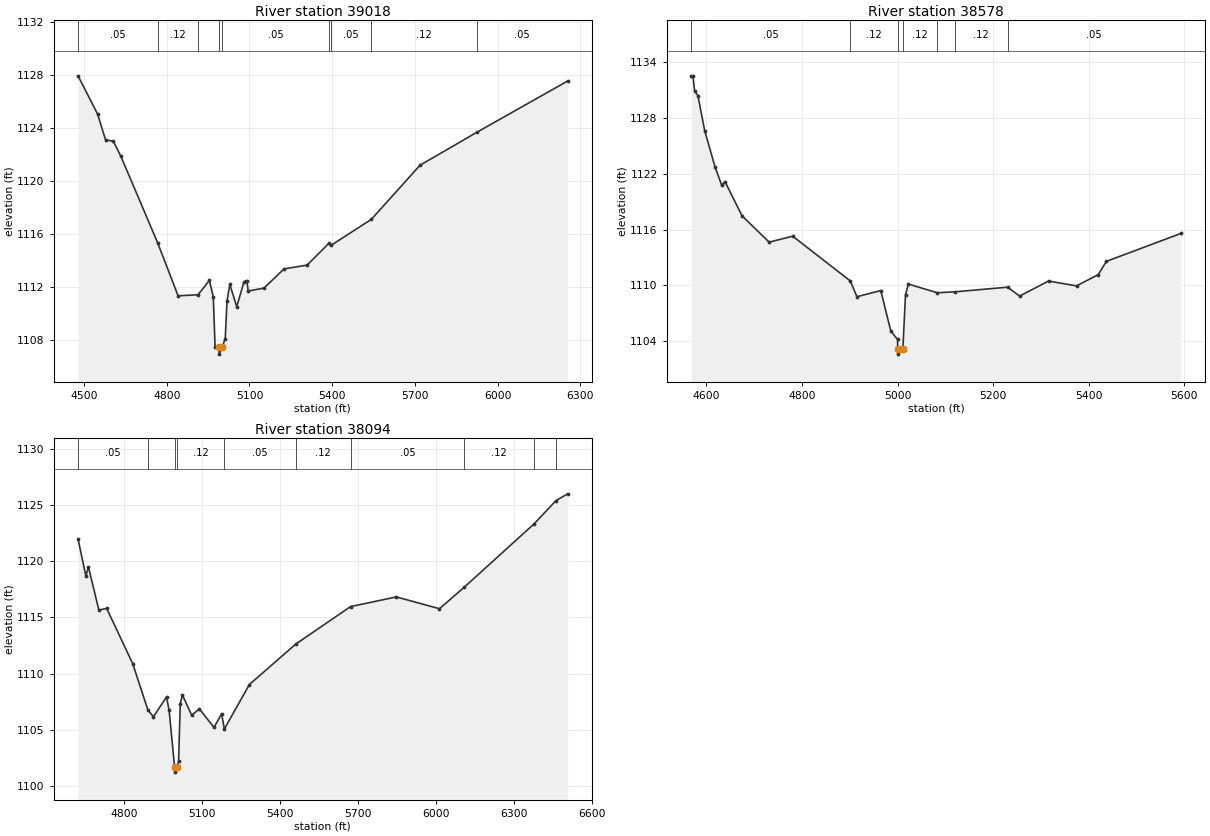
Type RM Length L Ch R = 1,39018,440,440,440
BEGIN DESCRIPTION:
MILLER CREEK 70.0
END DESCRIPTION:
XS GIS Cut Line= 3
      2865905.66     10269803.13      2865503.25     10270135.00
      2865205.69     10271353.08
#Sta/Elev= 30
  4478.4 1127.92  4549.4 1125.04  4578.1 1123.11  4606.7 1122.99  4634.0 1121.85
  4766.9 1115.36  4841.3 1111.36  4913.7 1111.44  4954.6 1112.52  4968.9 1111.29
  4975.4 1107.51  4989.8 1107.47  4990.3 1106.97  5000.5 1107.47  5012.2 1108.13
  5018.6 1110.97  5028.9 1112.22  5053.8 1110.54  5080.4 1112.43  5090.3 1112.51
  5095.5 1111.72  5152.5 1111.94  5225.6 1113.39  5308.9 1113.67  5388.4 1115.32
  5395.2 1115.15  5541.7 1117.11  5718.6 1121.19  5923.7 1123.66  6253.9 1127.53
#Mann=9,-1,0
  4478.4    0.05       0  4766.9    0.12       0  4913.7    0.05       0
  4989.8    0.05       0  5000.5    0.05       0  5388.4    0.12       0
  5395.2    0.05       0  5541.7    0.12       0  5923.7    0.05       0
Bank Sta=4989.8,5000.5
Exp/Cntr=0.3,0.1

Type RM Length L Ch R = 1,38578,484,484,484
BEGIN DESCRIPTION:
MILLER CREEK 69.0
END DESCRIPTION:
XS GIS Cut Line= 3
      2865655.65     10269453.14      2865340.75     10269748.00
      2864805.66     10270003.12
#Sta/Elev= 30
  4568.6 1132.56  4572.0 1132.56  4575.6 1130.93  4582.5 1130.42  4596.7 1126.64
  4618.1 1122.78  4632.3 1120.77  4639.1 1121.17  4674.8 1117.48  4731.5 1114.65
  4780.8 1115.29  4901.2 1110.47  4915.1 1108.77  4964.9 1109.44  4986.0 1105.07
  5000.0 1104.17  5000.4 1103.09  5000.9 1102.59  5011.1 1103.09  5016.7 1109.01
  5022.9 1110.13  5083.1 1109.20  5120.0 1109.30  5230.4 1109.80  5255.4 1108.84
  5315.8 1110.46  5374.4 1109.94  5419.8 1111.15  5436.9 1112.58  5592.8 1115.59
#Mann=7,-1,0
  4568.6    0.05       0  4901.2    0.12       0  5000.4    0.07       0
  5011.1    0.12       0  5083.1    0.05       0  5120.0    0.12       0
  5230.4    0.05       0
Bank Sta=5000.4,5011.1
Exp/Cntr=0.3,0.1

Type RM Length L Ch R = 1,38094,494,494,494
BEGIN DESCRIPTION:
MILLER CREEK 68.0
END DESCRIPTION:
XS GIS Cut Line= 3
      2865505.73     10269303.11      2865128.25     10269323.00
      2863905.69     10270203.11
#Sta/Elev= 30
  4622.0 1122.00  4652.1 1118.69  4662.1 1119.50  4702.2 1115.66  4732.2 1115.81
  4832.3 1110.90  4891.0 1106.76  4912.4 1106.16  4962.5 1107.93  4972.5 1106.75
  4993.4 1101.73  4993.9 1101.23  5004.2 1101.73  5009.0 1102.21  5015.5 1107.34
  5023.8 1108.10  5059.4 1106.30  5088.8 1106.86  5145.3 1105.21  5174.7 1106.43
  5185.0 1105.07  5281.5 1109.03  5459.9 1112.63  5670.9 1115.97  5847.3 1116.83
  6013.0 1115.78  6107.7 1117.68  6376.9 1123.33  6461.6 1125.41  6506.4 1126.01
#Mann=10,-1,0
  4622.0    0.05       0  4891.0    0.12       0  4993.4    0.07       0
  5004.2    0.12       0  5185.0    0.05       0  5459.9    0.12       0
  5670.9    0.05       0  6107.7    0.12       0  6376.9    0.05       0
  6461.6    0.12       0
Bank Sta=4993.4,5004.2
Exp/Cntr=0.3,0.1