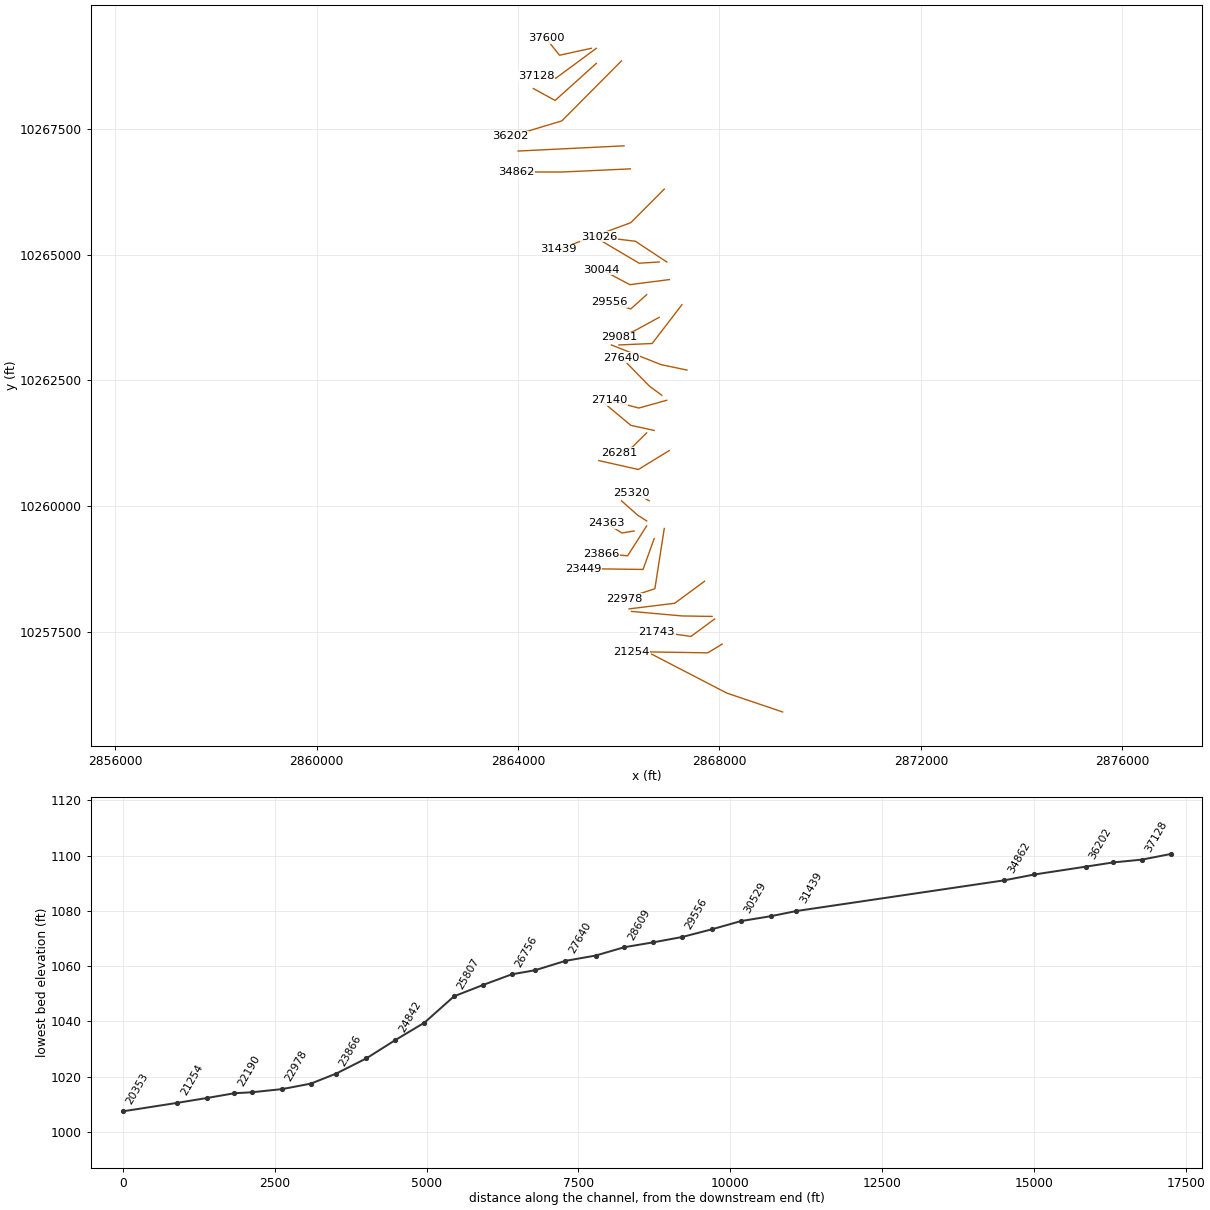
HEC-RAS study MILLER CREEK.prj: MILLER CREEK Base Level Engineering

--- MILLER CREEK.g01 (geometry) --- (continued)

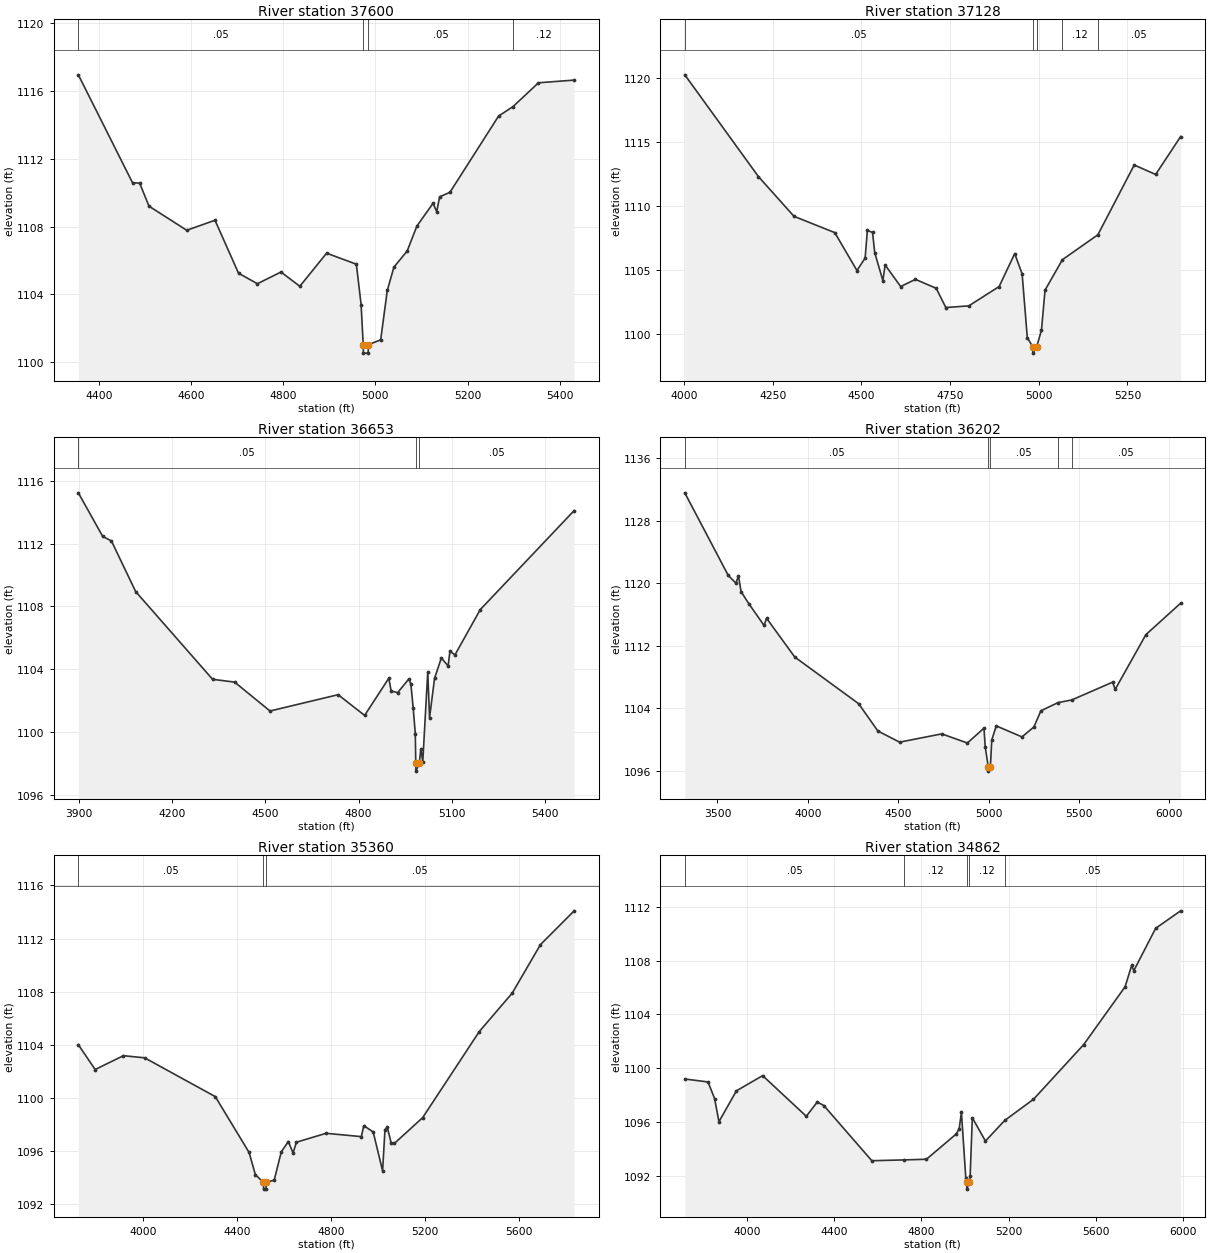
Type RM Length L Ch R = 1,37600,472,472,472
BEGIN DESCRIPTION:
MILLER CREEK 67.0
END DESCRIPTION:
XS GIS Cut Line= 3
      2865455.71     10269103.12      2864825.25     10268966.00
      2864555.71     10269303.08
#Sta/Elev= 30
  4354.8 1116.94  4472.5 1110.58  4487.9 1110.56  4508.3 1109.20  4590.2 1107.78
  4651.6 1108.37  4702.7 1105.25  4743.7 1104.63  4794.9 1105.32  4835.8 1104.48
  4894.0 1106.43  4958.6 1105.78  4968.9 1103.40  4973.5 1101.04  4974.0 1100.54
  4984.2 1100.54  4984.7 1101.04  5011.4 1101.32  5025.8 1104.24  5040.2 1105.61
  5069.0 1106.56  5089.9 1108.02  5125.1 1109.37  5133.1 1108.88  5139.5 1109.75
  5161.9 1110.02  5267.5 1114.51  5298.9 1115.07  5354.0 1116.47  5431.6 1116.63
#Mann=4,-1,0
  4354.8    0.05       0  4973.5    0.05       0  4984.7    0.05       0
  5298.9    0.12       0
Bank Sta=4973.5,4984.7
Exp/Cntr=0.3,0.1

Type RM Length L Ch R = 1,37128,475,475,475
BEGIN DESCRIPTION:
MILLER CREEK 66.0
END DESCRIPTION:
XS GIS Cut Line= 3
      2865555.65     10269103.09      2864753.25     10268510.00
      2864355.68     10268553.11
#Sta/Elev= 30
  4002.2 1120.25  4209.9 1112.30  4310.1 1109.20  4425.0 1107.93  4487.5 1104.97
  4510.5 1105.94  4516.8 1108.10  4531.4 1107.94  4537.6 1106.37  4560.6 1104.18
  4566.9 1105.40  4610.7 1103.72  4652.4 1104.28  4711.0 1103.58  4738.0 1102.08
  4802.8 1102.21  4888.3 1103.72  4932.2 1106.29  4953.1 1104.71  4967.7 1099.73
  4982.9 1099.02  4983.4 1098.52  4994.2 1099.02  5007.6 1100.31  5017.7 1103.44
  5066.8 1105.82  5166.6 1107.76  5269.1 1113.21  5329.5 1112.47  5399.9 1115.43
#Mann=5,-1,0
  4002.2    0.05       0  4982.9    0.05       0  4994.2    0.05       0
  5066.8    0.12       0  5166.6    0.05       0
Bank Sta=4982.9,4994.2
Exp/Cntr=0.3,0.1

Type RM Length L Ch R = 1,36653,451,451,451
BEGIN DESCRIPTION:
MILLER CREEK 65.0
END DESCRIPTION:
XS GIS Cut Line= 3
      2865555.71     10268803.13      2864737.75     10268066.00
      2864305.64     10268303.13
#Sta/Elev= 30
  3898.9 1115.23  3977.0 1112.46  4005.4 1112.16  4083.2 1108.94  4330.5 1103.35
  4401.5 1103.17  4515.1 1101.33  4734.1 1102.37  4819.3 1101.05  4897.1 1103.42
  4904.5 1102.61  4925.5 1102.50  4961.3 1103.37  4968.0 1103.05  4975.5 1101.51
  4982.2 1099.89  4983.7 1098.00  4984.2 1097.50  4995.0 1098.00  5000.0 1098.93
  5006.2 1098.11  5022.3 1103.83  5028.0 1100.90  5044.1 1103.41  5065.9 1104.71
  5087.7 1104.20  5093.6 1105.15  5109.5 1104.90  5191.0 1107.79  5492.9 1114.10
#Mann=3,-1,0
  3898.9    0.05       0  4983.7    0.03       0  4995.0    0.05       0
Bank Sta=4983.7,4995
Exp/Cntr=0.3,0.1

Type RM Length L Ch R = 1,36202,842,842,842
BEGIN DESCRIPTION:
MILLER CREEK 64.0
END DESCRIPTION:
XS GIS Cut Line= 3
      2866055.69     10268853.12      2864872.25     10267660.00
      2863855.66     10267353.11
#Sta/Elev= 30
  3319.5 1131.60  3559.9 1121.02  3602.3 1120.04  3616.5 1120.98  3630.6 1118.95
  3673.0 1117.43  3757.9 1114.62  3772.0 1115.54  3927.6 1110.58  4281.2 1104.60
  4387.3 1101.11  4507.5 1099.68  4740.8 1100.74  4882.3 1099.57  4974.2 1101.47
  4981.3 1099.03  4998.4 1096.47  4998.9 1095.97  5009.7 1096.47  5017.3 1099.96
  5042.3 1101.76  5184.6 1100.35  5250.5 1101.63  5288.9 1103.69  5383.6 1104.74
  5459.6 1105.08  5685.8 1107.36  5700.0 1106.44  5870.1 1113.45  6061.9 1117.47
#Mann=5,-1,0
  3319.5    0.05       0  4998.4    0.03       0  5009.7    0.05       0
  5383.6    0.12       0  5459.6    0.05       0
Bank Sta=4998.4,5009.7
Exp/Cntr=0.3,0.1

Type RM Length L Ch R = 1,35360,498,498,498
BEGIN DESCRIPTION:
Mapping XS 20792461
END DESCRIPTION:
XS GIS Cut Line= 2
      2866107.01     10267163.89      2864002.79     10267059.73
#Sta/Elev= 30
  3725.9 1104.02  3797.3 1102.15  3917.5 1103.19  4007.6 1103.03  4307.9 1100.11
  4451.4 1095.91  4478.1 1094.24  4512.5 1093.65  4513.0 1093.15  4523.4 1093.15
  4523.9 1093.65  4558.2 1093.83  4588.3 1095.96  4618.3 1096.73  4638.3 1095.87
  4652.6 1096.68  4778.5 1097.35  4928.7 1097.10  4938.7 1097.93  4978.8 1097.45
  5018.8 1094.52  5028.8 1097.63  5038.8 1097.80  5055.1 1096.64  5068.9 1096.59
  5189.0 1098.53  5429.3 1105.00  5569.5 1107.90  5689.6 1111.55  5832.7 1114.09
#Mann=3,-1,0
  3725.9    0.05       0  4512.5    0.03       0  4523.9    0.05       0
Bank Sta=4512.5,4523.9
Exp/Cntr=0.3,0.1

Type RM Length L Ch R = 1,34862,3423,3423,3423
BEGIN DESCRIPTION:
Mapping XS 72102916
END DESCRIPTION:
XS GIS Cut Line= 3
      2866231.99     10266705.56      2864877.81     10266643.06
      2863961.14     10266643.06
#Sta/Elev= 30
  3715.7 1099.21  3822.1 1098.99  3852.2 1097.76  3872.2 1096.04  3952.3 1098.33
  4072.4 1099.46  4272.6 1096.44  4322.7 1097.50  4352.7 1097.24  4572.9 1093.14
  4721.5 1093.20  4823.2 1093.25  4960.0 1095.13  4973.3 1095.53  4983.4 1096.74
  5003.4 1091.89  5007.7 1091.53  5008.2 1091.03  5019.1 1091.53  5023.4 1092.01
  5033.4 1096.33  5093.5 1094.60  5181.7 1096.13  5313.5 1097.70  5543.5 1101.76
  5733.5 1106.06  5763.5 1107.64  5773.5 1107.26  5873.5 1110.40  5988.0 1111.70
#Mann=5,-1,0
  3715.7    0.05       0  4721.5    0.12       0  5007.7    0.07       0
  5019.1    0.12       0  5181.7    0.05       0
Bank Sta=5007.7,5019.1
Exp/Cntr=0.3,0.1

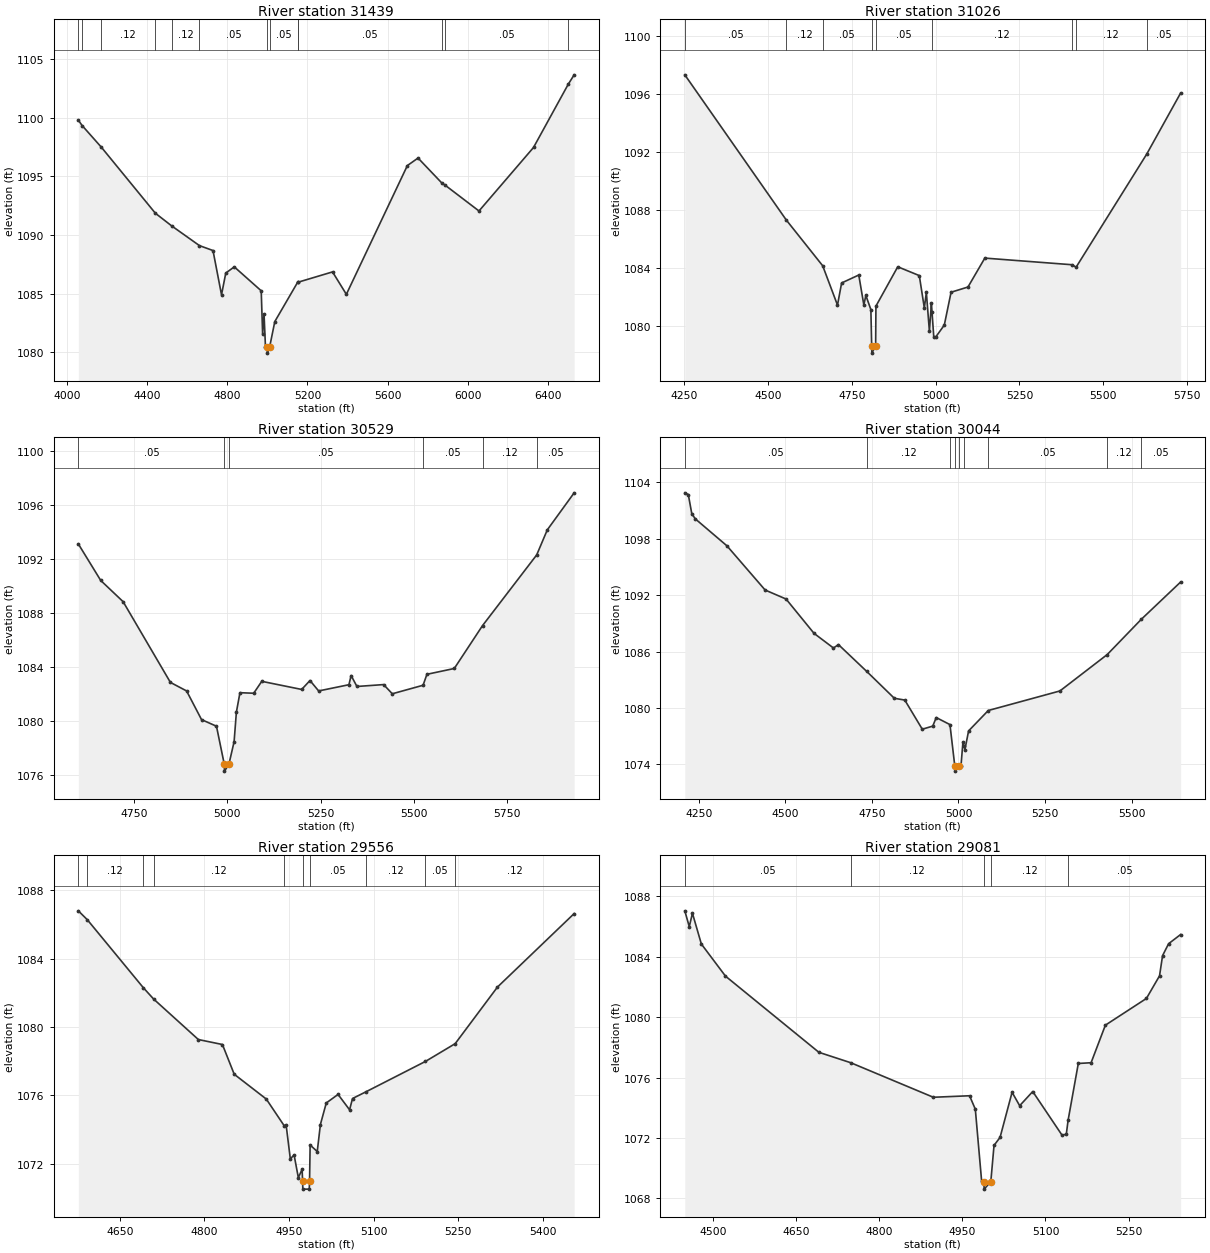
Type RM Length L Ch R = 1,31439,413,413,413
BEGIN DESCRIPTION:
MILLER CREEK 59.0
END DESCRIPTION:
XS GIS Cut Line= 3
      2866905.68     10266303.11      2866240.75     10265635.00
      2864805.65     10265103.10
#Sta/Elev= 30
  4057.4 1099.78  4076.3 1099.32  4172.4 1097.47  4441.6 1091.85  4522.2 1090.78
  4661.5 1089.09  4729.1 1088.67  4771.6 1084.90  4792.8 1086.75  4835.2 1087.28
  4969.6 1085.24  4976.6 1081.58  4983.7 1083.26  4990.8 1080.48  4999.5 1080.43
  5000.0 1079.93  5011.3 1080.43  5037.4 1082.62  5150.7 1085.95  5153.2 1085.97
  5325.3 1086.85  5394.3 1084.94  5698.6 1095.91  5751.9 1096.55  5869.0 1094.45
  5885.2 1094.26  6055.8 1092.04  6327.8 1097.45  6501.1 1102.84  6530.5 1103.64
#Mann=13,-1,0
  4057.4    0.12       0  4076.3    0.05       0  4172.4    0.12       0
  4441.6    0.05       0  4522.2    0.12       0  4661.5    0.05       0
  4999.5    0.05       0  5011.3    0.05       0  5150.7    0.12       0
  5153.2    0.05       0  5869.0    0.12       0  5885.2    0.05       0
  6501.1    0.12       0
Bank Sta=4999.5,5011.3
Exp/Cntr=0.3,0.1

Type RM Length L Ch R = 1,31026,497,497,497
BEGIN DESCRIPTION:
MILLER CREEK 58.0
END DESCRIPTION:
XS GIS Cut Line= 3
      2866955.69     10264853.11      2866331.25     10265266.00
      2865605.66     10265353.11
#Sta/Elev= 30
  4251.4 1097.33  4554.3 1087.29  4662.8 1084.13  4707.0 1081.41  4719.3 1082.94
  4770.5 1083.49  4785.6 1081.42  4791.6 1082.08  4806.6 1081.10  4809.0 1078.59
  4809.5 1078.09  4820.8 1078.59  4821.7 1081.34  4886.8 1084.06  4951.1 1083.45
  4966.1 1081.21  4972.1 1082.29  4981.2 1079.61  4987.2 1081.53  4989.1 1080.91
  4994.3 1079.20  5000.0 1079.20  5025.7 1080.03  5045.9 1082.30  5096.3 1082.66
  5146.6 1084.66  5407.2 1084.20  5418.9 1084.03  5629.4 1091.84  5730.8 1096.07
#Mann=9,-1,0
  4251.4    0.05       0  4554.3    0.12       0  4662.8    0.05       0
  4809.0    0.07       0  4820.8    0.05       0  4989.1    0.12       0
  5407.2    0.05       0  5418.9    0.12       0  5629.4    0.05       0
Bank Sta=4809,4820.8
Exp/Cntr=0.3,0.1

Type RM Length L Ch R = 1,30529,485,485,485
BEGIN DESCRIPTION:
MILLER CREEK 57.0
END DESCRIPTION:
XS GIS Cut Line= 3
      2866805.67     10264853.11      2866406.50     10264829.00
      2865605.72     10265303.09
#Sta/Elev= 30
  4600.1 1093.10  4660.2 1090.40  4720.3 1088.83  4847.2 1082.86  4890.6 1082.23
  4930.7 1080.11  4970.8 1079.62  4991.8 1076.80  4992.3 1076.30  5004.1 1076.80
  5018.1 1078.48  5024.2 1080.66  5033.8 1082.10  5070.7 1082.06  5092.3 1082.94
  5199.4 1082.34  5221.7 1083.00  5245.0 1082.23  5326.2 1082.69  5332.1 1083.37
  5347.7 1082.56  5419.3 1082.70  5442.6 1082.02  5525.2 1082.65  5535.5 1083.46
  5608.9 1083.89  5684.7 1087.06  5830.1 1092.29  5858.5 1094.14  5930.6 1096.88
#Mann=6,-1,0
  4600.1    0.05       0  4991.8    0.05       0  5004.1    0.05       0
  5525.2    0.05       0  5684.7    0.12       0  5830.1    0.05       0
Bank Sta=4991.8,5004.1
Exp/Cntr=0.3,0.1

Type RM Length L Ch R = 1,30044,488,488,488
BEGIN DESCRIPTION:
MILLER CREEK 56.0
END DESCRIPTION:
XS GIS Cut Line= 3
      2867005.70     10264503.11      2866222.00     10264402.00
      2865655.68     10264703.12
#Sta/Elev= 30
  4209.8 1102.90  4219.9 1102.72  4230.0 1100.68  4240.1 1100.13  4331.5 1097.26
  4441.7 1092.56  4502.2 1091.60  4582.9 1087.95  4639.0 1086.39  4653.5 1086.75
  4735.3 1083.89  4814.8 1081.04  4845.0 1080.85  4895.5 1077.75  4925.7 1078.08
  4935.8 1078.99  4975.4 1078.24  4989.5 1073.79  4990.0 1073.29  5001.8 1073.79
  5007.2 1073.83  5012.9 1076.39  5016.2 1075.93  5018.6 1075.59  5029.2 1077.57
  5086.0 1079.74  5292.9 1081.82  5429.4 1085.69  5527.5 1089.43  5641.4 1093.41
#Mann=9,-1,0
  4209.8    0.05       0  4735.3    0.12       0  4975.4    0.05       0
  4989.5    0.05       0  5001.8    0.05       0  5016.2    0.12       0
  5086.0    0.05       0  5429.4    0.12       0  5527.5    0.05       0
Bank Sta=4989.5,5001.8
Exp/Cntr=0.3,0.1

Type RM Length L Ch R = 1,29556,475,475,475
BEGIN DESCRIPTION:
MILLER CREEK 55.0
END DESCRIPTION:
XS GIS Cut Line= 3
      2866555.69     10264203.12      2866241.00     10263920.00
      2865805.70     10264053.11
#Sta/Elev= 30
  4576.7 1086.80  4592.6 1086.28  4691.9 1082.30  4710.1 1081.64  4789.4 1079.27
  4832.0 1078.98  4852.9 1077.24  4909.7 1075.79  4941.4 1074.23  4944.8 1074.29
  4952.3 1072.29  4959.0 1072.52  4966.5 1071.19  4973.2 1071.68  4974.0 1071.02
  4974.5 1070.52  4985.9 1070.52  4986.4 1071.02  4987.4 1073.10  5000.0 1072.72
  5005.6 1074.30  5016.0 1075.56  5036.9 1076.06  5057.3 1075.16  5062.5 1075.82
  5086.1 1076.21  5191.7 1077.99  5244.4 1079.03  5319.3 1082.34  5455.2 1086.64
#Mann=10,-1,0
  4576.7    0.05       0  4592.6    0.12       0  4691.9    0.05       0
  4710.1    0.12       0  4941.4    0.05       0  4974.0    0.05       0
  4986.4    0.05       0  5086.1    0.12       0  5191.7    0.05       0
  5244.4    0.12       0
Bank Sta=4974,4986.4
Exp/Cntr=0.3,0.1

Type RM Length L Ch R = 1,29081,472,472,472
BEGIN DESCRIPTION:
MILLER CREEK 54.0
END DESCRIPTION:
XS GIS Cut Line= 3
      2866805.72     10263753.13      2866322.25     10263488.00
      2866005.69     10263353.11
#Sta/Elev= 30
  4448.6 1087.05  4456.7 1086.00  4462.4 1086.89  4478.5 1084.85  4522.1 1082.72
  4690.8 1077.67  4748.3 1076.98  4897.5 1074.69  4962.9 1074.79  4973.3 1073.90
  4984.7 1069.13  4988.8 1069.10  4989.3 1068.60  5001.3 1069.10  5007.1 1071.50
  5018.0 1072.03  5039.7 1075.02  5053.4 1074.13  5077.0 1075.07  5129.7 1072.19
  5137.6 1072.23  5140.9 1073.17  5159.3 1076.93  5182.4 1076.98  5208.2 1079.47
  5282.3 1081.24  5306.0 1082.74  5311.5 1084.08  5322.4 1084.87  5344.1 1085.48
#Mann=5,-1,0
  4448.6    0.05       0  4748.3    0.12       0  4988.8    0.07       0
  5001.3    0.12       0  5140.9    0.05       0
Bank Sta=4988.8,5001.3
Exp/Cntr=0.3,0.1

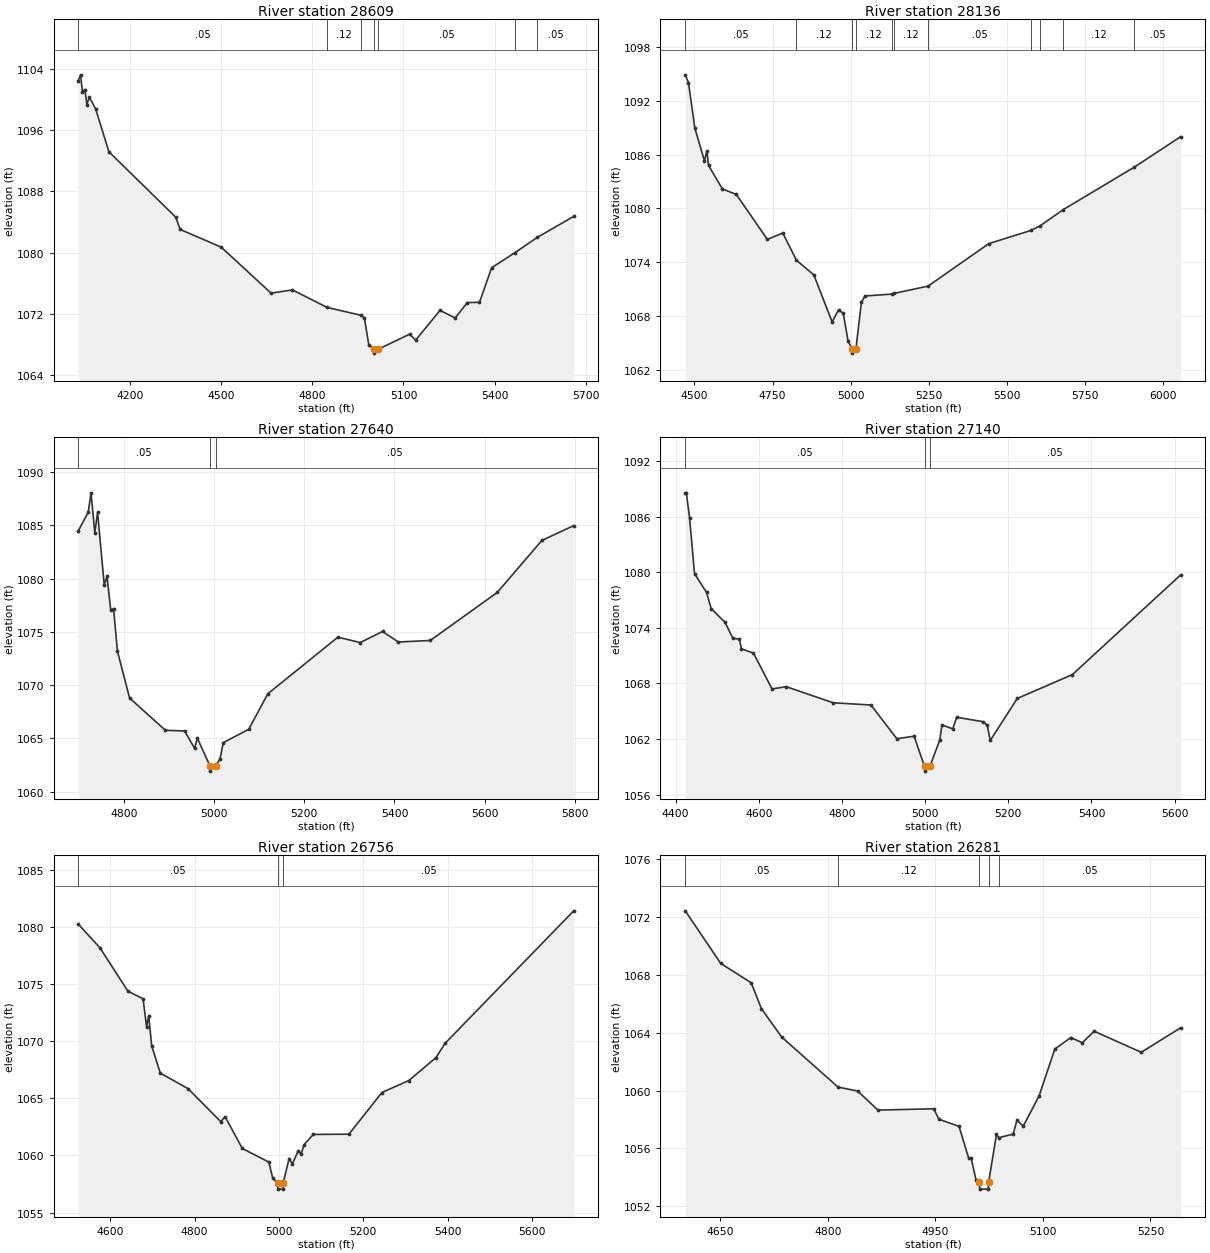
Type RM Length L Ch R = 1,28609,473,473,473
BEGIN DESCRIPTION:
MILLER CREEK 53.0
END DESCRIPTION:
XS GIS Cut Line= 3
      2867255.69     10264003.12      2866665.75     10263232.00
      2866005.68     10263203.11
#Sta/Elev= 30
  4029.1 1102.51  4036.4 1103.26  4042.7 1101.06  4050.9 1101.34  4057.2 1099.36
  4065.4 1100.33  4086.2 1098.80  4129.8 1093.20  4350.1 1084.63  4364.6 1083.03
  4499.7 1080.72  4663.8 1074.70  4734.5 1075.12  4848.3 1072.83  4959.2 1071.81
  4971.3 1071.47  4985.8 1067.92  5003.8 1067.35  5004.3 1066.85  5016.3 1067.35
  5120.2 1069.33  5140.2 1068.55  5220.3 1072.44  5270.3 1071.45  5310.4 1073.47
  5350.4 1073.49  5390.4 1078.02  5467.2 1080.00  5541.0 1082.00  5660.7 1084.74
#Mann=7,-1,0
  4029.1    0.05       0  4848.3    0.12       0  4959.2    0.05       0
  5003.8    0.03       0  5016.3    0.05       0  5467.2    0.12       0
  5541.0    0.05       0
Bank Sta=5003.8,5016.3
Exp/Cntr=0.3,0.1

Type RM Length L Ch R = 1,28136,496,496,496
BEGIN DESCRIPTION:
MILLER CREEK 52.0
END DESCRIPTION:
XS GIS Cut Line= 3
      2867355.72     10262703.10      2866837.75     10262813.00
      2865855.70     10263203.11
#Sta/Elev= 30
  4470.5 1094.93  4480.8 1094.07  4501.2 1088.97  4531.9 1085.32  4539.9 1086.42
  4545.0 1084.80  4589.5 1082.18  4634.1 1081.56  4733.4 1076.54  4783.0 1077.25
  4826.2 1074.22  4882.3 1072.57  4940.8 1067.31  4961.2 1068.66  4976.5 1068.28
  4991.9 1065.16  5004.3 1064.33  5004.8 1063.83  5017.1 1064.33  5034.5 1069.52
  5045.8 1070.22  5133.5 1070.43  5139.9 1070.51  5248.0 1071.32  5442.6 1076.07
  5577.6 1077.54  5606.9 1078.06  5680.5 1079.86  5908.5 1084.62  6056.7 1088.02
#Mann=11,-1,0
  4470.5    0.05       0  4826.2    0.12       0  5004.3    0.07       0
  5017.1    0.12       0  5133.5    0.05       0  5139.9    0.12       0
  5248.0    0.05       0  5577.6    0.12       0  5606.9    0.05       0
  5680.5    0.12       0  5908.5    0.05       0
Bank Sta=5004.3,5017.1
Exp/Cntr=0.3,0.1

Type RM Length L Ch R = 1,27640,500,500,500
BEGIN DESCRIPTION:
MILLER CREEK 51.0
END DESCRIPTION:
XS GIS Cut Line= 3
      2866855.69     10262203.11      2866612.75     10262382.00
      2866055.69     10262953.11
#Sta/Elev= 30
  4698.3 1084.50  4720.3 1086.25  4726.5 1088.07  4734.9 1084.33  4741.1 1086.23
  4755.8 1079.43  4762.0 1080.21  4770.4 1077.03  4776.6 1077.20  4785.0 1073.21
  4812.1 1068.79  4891.5 1065.76  4934.3 1065.69  4956.3 1064.07  4962.5 1065.02
  4990.3 1062.42  4990.8 1061.92  5003.1 1062.42  5012.9 1063.06  5019.9 1064.59
  5076.5 1065.85  5118.9 1069.19  5274.5 1074.51  5323.9 1074.00  5373.5 1075.04
  5408.8 1074.05  5479.5 1074.20  5628.1 1078.71  5727.2 1083.60  5797.8 1084.99
#Mann=3,-1,0
  4698.3    0.05       0  4990.3    0.05       0  5003.1    0.05       0
Bank Sta=4990.3,5003.1
Exp/Cntr=0.3,0.1

Type RM Length L Ch R = 1,27140,384,384,384
BEGIN DESCRIPTION:
MILLER CREEK 50.0
END DESCRIPTION:
XS GIS Cut Line= 3
      2866955.70     10262103.12      2866400.25     10261948.00
      2865805.65     10262103.12
#Sta/Elev= 30
  4423.3 1088.58  4425.9 1088.58  4433.7 1085.88  4445.6 1079.86  4474.6 1077.82
  4485.6 1076.08  4519.1 1074.59  4537.5 1072.90  4553.3 1072.78  4558.5 1071.74
  4587.4 1071.27  4632.0 1067.40  4666.1 1067.65  4779.0 1065.91  4869.8 1065.67
  4932.1 1062.03  4973.6 1062.30  4998.7 1059.03  4999.2 1058.53  5011.6 1059.03
  5035.3 1061.90  5040.5 1063.51  5066.7 1063.10  5075.8 1064.35  5139.1 1063.87
  5149.4 1063.49  5156.7 1061.84  5221.7 1066.38  5354.0 1068.95  5614.5 1079.72
#Mann=3,-1,0
  4423.3    0.05       0  4998.7    0.05       0  5011.6    0.05       0
Bank Sta=4998.7,5011.6
Exp/Cntr=0.3,0.1

Type RM Length L Ch R = 1,26756,475,475,475
BEGIN DESCRIPTION:
MILLER CREEK 49.0
END DESCRIPTION:
XS GIS Cut Line= 3
      2866705.67     10261503.11      2866241.00     10261604.00
      2865705.65     10262053.14
#Sta/Elev= 30
  4524.5 1080.25  4575.7 1078.19  4642.2 1074.38  4678.0 1073.72  4686.3 1071.28
  4691.4 1072.21  4698.5 1069.58  4718.9 1067.21  4784.6 1065.85  4862.2 1062.96
  4872.4 1063.40  4913.3 1060.61  4976.1 1059.42  4985.0 1058.06  4997.0 1057.55
  4997.5 1057.05  5009.4 1057.05  5009.9 1057.55  5024.2 1059.73  5032.0 1059.27
  5046.1 1060.42  5052.8 1060.12  5059.4 1060.93  5081.5 1061.84  5166.0 1061.86
  5244.1 1065.51  5307.9 1066.56  5372.4 1068.57  5393.7 1069.81  5698.8 1081.42
#Mann=3,-1,0
  4524.5    0.05       0  4997.0    0.03       0  5009.9    0.05       0
Bank Sta=4997,5009.9
Exp/Cntr=0.3,0.1

Type RM Length L Ch R = 1,26281,474,474,474
BEGIN DESCRIPTION:
MILLER CREEK 48.0
END DESCRIPTION:
XS GIS Cut Line= 3
      2866555.70     10261453.13      2866272.00     10261173.00
      2866005.65     10261053.09
#Sta/Elev= 30
  4601.3 1072.44  4650.8 1068.80  4693.3 1067.46  4707.4 1065.68  4735.7 1063.71
  4814.4 1060.24  4841.7 1059.97  4870.0 1058.65  4947.8 1058.74  4954.9 1058.02
  4983.1 1057.52  4996.4 1055.34  5000.0 1055.34  5006.7 1053.82  5011.4 1053.68
  5011.9 1053.18  5023.9 1053.18  5024.4 1053.68  5035.3 1056.97  5038.6 1056.74
  5058.5 1056.99  5063.9 1057.95  5072.7 1057.55  5094.7 1059.63  5116.6 1062.87
  5138.9 1063.67  5155.0 1063.31  5171.4 1064.11  5237.2 1062.65  5292.1 1064.35
#Mann=5,-1,0
  4601.3    0.05       0  4814.4    0.12       0  5011.4    0.07       0
  5024.4    0.12       0  5038.6    0.05       0
Bank Sta=5011.4,5024.4
Exp/Cntr=0.3,0.1

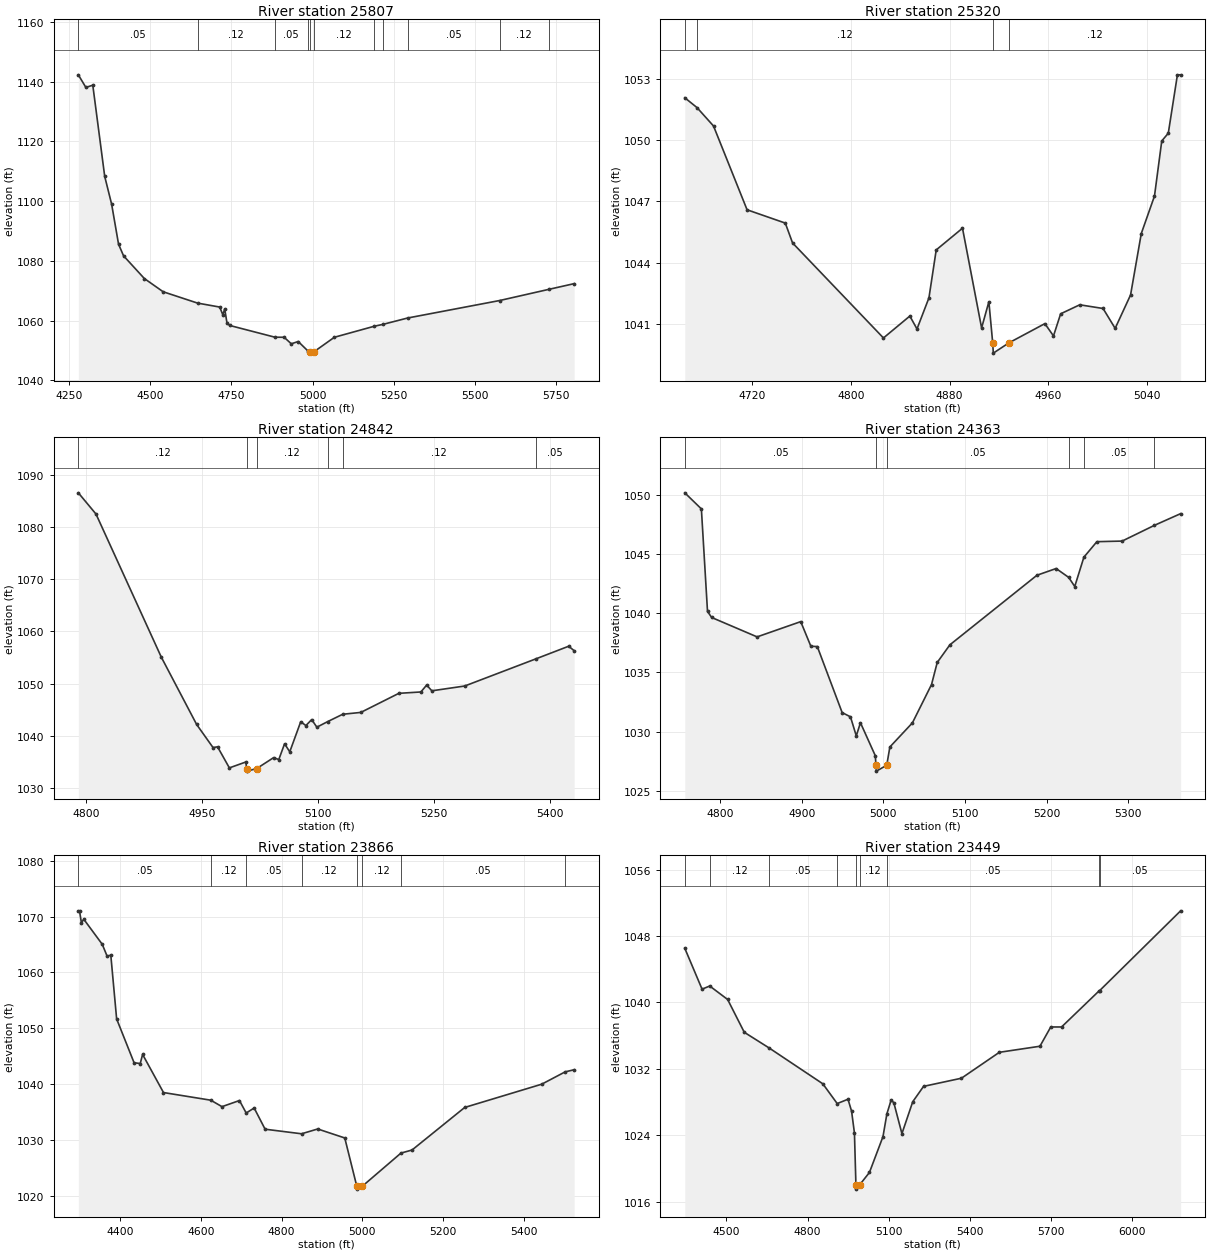
Type RM Length L Ch R = 1,25807,487,487,487
BEGIN DESCRIPTION:
MILLER CREEK 47.0
END DESCRIPTION:
XS GIS Cut Line= 3
      2867005.72     10261103.13      2866390.75     10260726.00
      2865605.68     10260903.11
#Sta/Elev= 30
  4278.6 1142.27  4301.8 1138.05  4323.1 1138.80  4359.8 1108.27  4381.1 1098.97
  4402.4 1085.57  4417.8 1081.68  4481.7 1074.09  4539.7 1069.65  4645.5 1065.86
  4713.8 1064.53  4723.4 1061.94  4729.2 1063.90  4736.1 1059.22  4744.6 1058.37
  4883.8 1054.44  4912.1 1054.42  4934.1 1052.23  4955.4 1053.00  4984.2 1049.95
  4991.4 1049.61  4991.9 1049.11  5004.5 1049.61  5066.7 1054.42  5190.2 1058.13
  5216.0 1058.73  5292.4 1060.87  5575.1 1066.71  5727.3 1070.47  5804.8 1072.37
#Mann=11,-1,0
  4278.6    0.05       0  4645.5    0.12       0  4883.8    0.05       0
  4984.2    0.12       0  4991.4    0.07       0  5004.5    0.12       0
  5190.2    0.05       0  5216.0    0.12       0  5292.4    0.05       0
  5575.1    0.12       0  5727.3    0.05       0
Bank Sta=4991.4,5004.5
Exp/Cntr=0.3,0.1

Type RM Length L Ch R = 1,25320,478,478,478
BEGIN DESCRIPTION:
MILLER CREEK 46.0
END DESCRIPTION:
XS GIS Cut Line= 3
      2866605.70     10260103.10      2866319.00     10260276.00
      2866255.71     10260253.12
#Sta/Elev= 30
  4665.2 1052.06  4675.1 1051.58  4688.5 1050.68  4715.7 1046.59  4746.7 1045.94
  4752.6 1044.97  4826.3 1040.33  4847.7 1041.40  4853.5 1040.77  4863.2 1042.29
  4869.1 1044.63  4890.4 1045.69  4905.9 1040.82  4911.8 1042.10  4914.9 1040.09
  4915.4 1039.59  4928.0 1040.09  4957.2 1041.03  4964.2 1040.43  4970.0 1041.51
  4985.5 1041.95  5004.4 1041.77  5014.2 1040.80  5026.7 1042.43  5035.4 1045.43
  5046.1 1047.26  5052.0 1049.95  5057.3 1050.33  5064.7 1053.18  5067.3 1053.18
#Mann=4,-1,0
  4665.2    0.05       0  4675.1    0.12       0  4914.9    0.07       0
  4928.0    0.12       0
Bank Sta=4914.9,4928
Exp/Cntr=0.3,0.1

Type RM Length L Ch R = 1,24842,479,479,479
BEGIN DESCRIPTION:
MILLER CREEK 45.0
END DESCRIPTION:
XS GIS Cut Line= 3
      2866555.68     10259703.11      2866378.25     10259816.00
      2866055.71     10260103.09
#Sta/Elev= 30
  4789.7 1086.50  4812.6 1082.44  4897.2 1055.08  4942.9 1042.23  4964.1 1037.82
  4970.0 1037.95  4985.3 1033.93  5006.7 1035.06  5007.6 1033.81  5008.1 1033.31
  5020.8 1033.81  5042.6 1035.89  5049.3 1035.52  5056.8 1038.54  5063.5 1037.00
  5077.7 1042.75  5084.4 1042.02  5091.9 1043.16  5098.6 1041.71  5112.4 1042.76
  5132.1 1044.18  5155.5 1044.53  5204.8 1048.18  5233.3 1048.44  5240.8 1049.76
  5247.5 1048.66  5290.1 1049.58  5382.1 1054.76  5424.7 1057.18  5431.8 1056.33
#Mann=6,-1,0
  4789.7    0.12       0  5007.6    0.07       0  5020.8    0.12       0
  5112.4    0.05       0  5132.1    0.12       0  5382.1    0.05       0
Bank Sta=5007.6,5020.8
Exp/Cntr=0.3,0.1

Type RM Length L Ch R = 1,24363,497,497,497
BEGIN DESCRIPTION:
MILLER CREEK 44.0
END DESCRIPTION:
XS GIS Cut Line= 3
      2866305.67     10259503.11      2866066.00     10259463.00
      2865755.70     10259653.10
#Sta/Elev= 30
  4757.0 1050.19  4777.3 1048.83  4784.8 1040.16  4789.9 1039.65  4845.5 1038.01
  4898.9 1039.30  4911.3 1037.22  4919.2 1037.19  4949.6 1031.61  4959.8 1031.25
  4966.9 1029.64  4972.0 1030.75  4990.2 1027.96  4991.0 1027.16  4991.5 1026.66
  5004.2 1027.16  5008.0 1028.70  5035.6 1030.74  5059.0 1033.98  5066.0 1035.85
  5081.5 1037.34  5188.0 1043.22  5211.5 1043.79  5226.9 1043.04  5234.3 1042.27
  5245.5 1044.75  5261.4 1046.06  5292.3 1046.11  5331.8 1047.44  5363.9 1048.43
#Mann=6,-1,0
  4757.0    0.05       0  4991.0    0.05       0  5004.2    0.05       0
  5226.9    0.12       0  5245.5    0.05       0  5331.8    0.12       0
Bank Sta=4991,5004.2
Exp/Cntr=0.3,0.1

Type RM Length L Ch R = 1,23866,417,417,417
BEGIN DESCRIPTION:
MILLER CREEK 43.0
END DESCRIPTION:
XS GIS Cut Line= 3
      2866555.67     10259603.09      2866178.25     10259010.00
      2865655.73     10259053.11
#Sta/Elev= 30
  4297.0 1071.04  4299.9 1071.04  4304.6 1068.91  4310.5 1069.53  4356.2 1065.04
  4368.1 1062.94  4377.4 1063.08  4391.8 1051.67  4435.0 1043.81  4450.2 1043.67
  4456.1 1045.30  4507.8 1038.47  4624.8 1037.10  4652.6 1035.94  4695.8 1037.04
  4712.5 1034.80  4732.2 1035.70  4759.3 1031.90  4849.5 1031.08  4889.6 1031.94
  4956.5 1030.33  4986.3 1021.66  4986.8 1021.16  4999.6 1021.66  5095.6 1027.62
  5123.0 1028.17  5253.4 1035.80  5444.1 1039.97  5502.1 1042.18  5524.3 1042.56
#Mann=8,-1,0
  4297.0    0.05       0  4624.8    0.12       0  4712.5    0.05       0
  4849.5    0.12       0  4986.3    0.07       0  4999.6    0.12       0
  5095.6    0.05       0  5502.1    0.12       0
Bank Sta=4986.3,4999.6
Exp/Cntr=0.3,0.1

Type RM Length L Ch R = 1,23449,471,471,471
BEGIN DESCRIPTION:
MILLER CREEK 42.0
END DESCRIPTION:
XS GIS Cut Line= 3
      2866705.69     10259353.14      2866484.50     10258738.00
      2865305.70     10258753.11
#Sta/Elev= 30
  4346.3 1046.52  4410.1 1041.60  4438.4 1041.98  4504.6 1040.36  4566.1 1036.41
  4658.1 1034.52  4856.4 1030.21  4909.6 1027.83  4949.5 1028.35  4962.7 1026.92
  4973.3 1024.29  4978.8 1018.03  4979.3 1017.53  4992.2 1018.03  5028.8 1019.54
  5078.8 1023.85  5093.3 1026.60  5108.8 1028.23  5118.8 1027.94  5148.8 1024.21
  5188.8 1028.05  5228.8 1029.90  5368.8 1030.88  5508.9 1034.00  5658.9 1034.73
  5698.9 1037.05  5738.9 1037.05  5877.5 1041.39  5879.4 1041.42  6178.9 1051.03
#Mann=9,-1,0
  4346.3    0.05       0  4438.4    0.12       0  4658.1    0.05       0
  4909.6    0.12       0  4978.8    0.07       0  4992.2    0.12       0
  5093.3    0.05       0  5877.5    0.12       0  5879.4    0.05       0
Bank Sta=4978.8,4992.2
Exp/Cntr=0.3,0.1

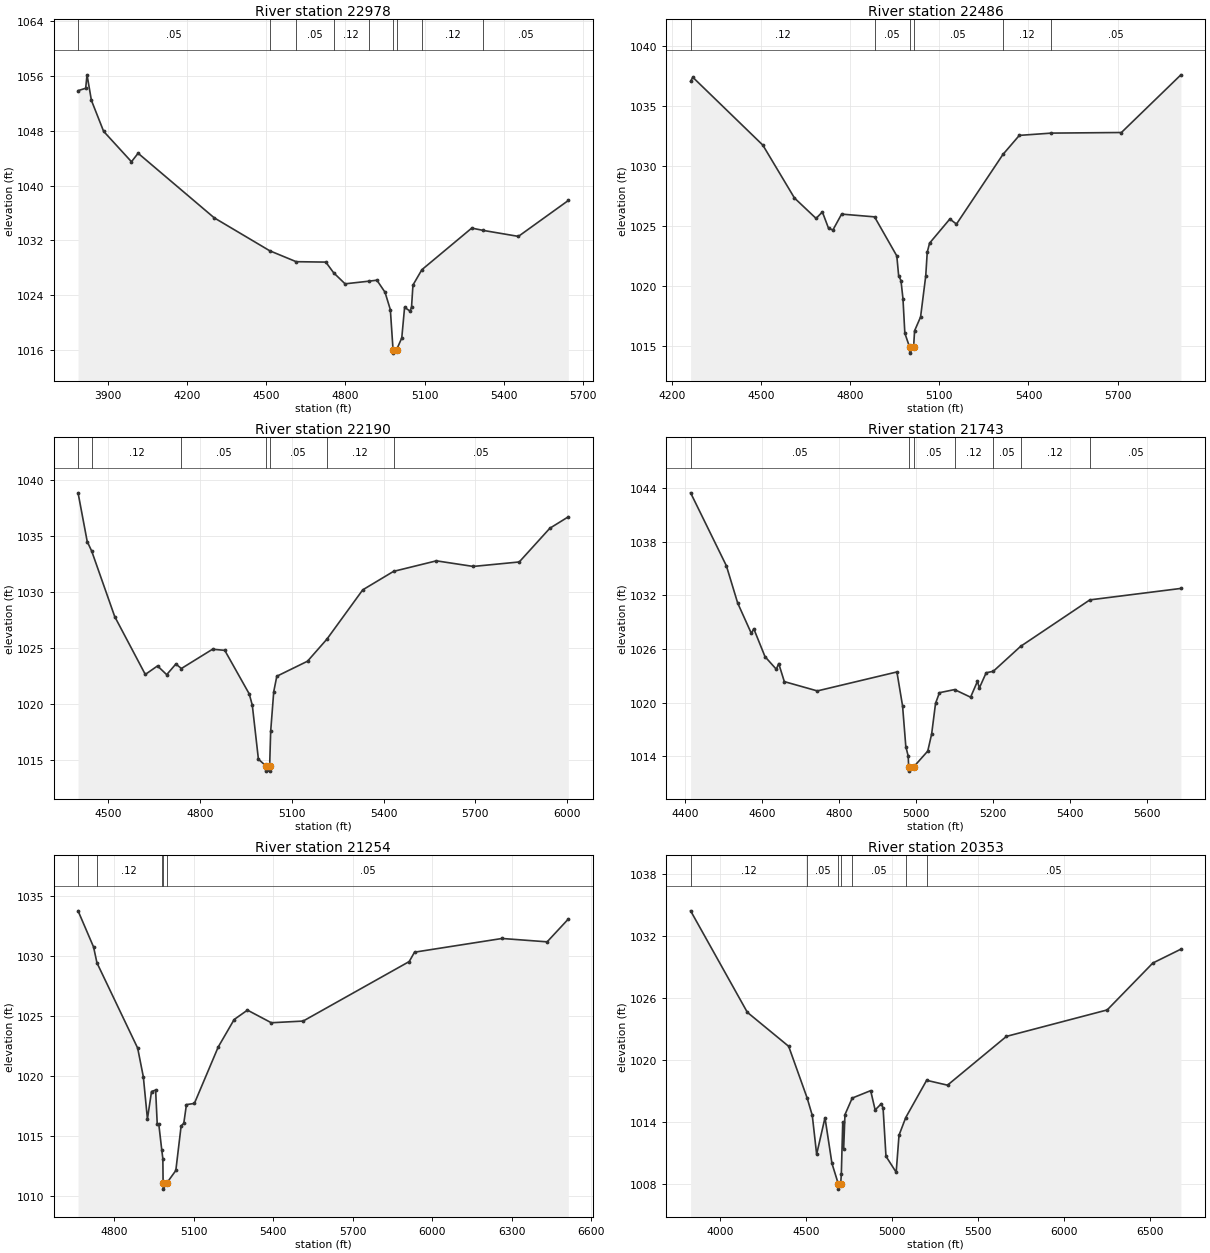
Type RM Length L Ch R = 1,22978,492,492,492
BEGIN DESCRIPTION:
MILLER CREEK 41.0
END DESCRIPTION:
XS GIS Cut Line= 3
      2866905.69     10259553.15      2866719.00     10258354.00
      2866105.66     10258153.10
#Sta/Elev= 30
  3786.4 1053.85  3815.3 1054.20  3820.4 1056.16  3837.0 1052.44  3883.3 1047.92
  3988.9 1043.48  4014.1 1044.72  4302.6 1035.30  4513.3 1030.49  4613.4 1028.90
  4725.8 1028.84  4755.5 1027.28  4798.8 1025.67  4889.9 1026.06  4919.5 1026.20
  4950.3 1024.44  4970.5 1021.90  4980.7 1016.06  4981.2 1015.56  4994.1 1016.06
  5013.8 1017.77  5024.5 1022.24  5045.6 1021.68  5050.9 1022.31  5056.2 1025.49
  5090.0 1027.73  5279.1 1033.80  5323.0 1033.46  5456.0 1032.59  5645.4 1037.83
#Mann=9,-1,0
  3786.4    0.05       0  4513.3    0.12       0  4613.4    0.05       0
  4755.5    0.12       0  4889.9    0.05       0  4980.7    0.03       0
  4994.1    0.05       0  5090.0    0.12       0  5323.0    0.05       0
Bank Sta=4980.7,4994.1
Exp/Cntr=0.3,0.1

Type RM Length L Ch R = 1,22486,296,296,296
BEGIN DESCRIPTION:
MILLER CREEK 40.0
END DESCRIPTION:
XS GIS Cut Line= 3
      2867705.65     10258503.09      2867112.00     10258065.00
      2866205.68     10257953.11
#Sta/Elev= 30
  4262.2 1037.04  4269.5 1037.38  4505.4 1031.73  4611.9 1027.33  4684.7 1025.63
  4705.9 1026.17  4726.8 1024.80  4741.4 1024.67  4770.7 1025.99  4881.6 1025.76
  4956.5 1022.51  4962.7 1020.88  4970.6 1020.45  4977.3 1018.95  4983.6 1016.08
  4999.6 1014.92  5000.1 1014.42  5013.1 1014.92  5016.4 1016.28  5036.6 1017.43
  5054.0 1020.85  5059.0 1022.81  5066.8 1023.57  5135.1 1025.58  5157.5 1025.16
  5313.8 1030.95  5369.1 1032.54  5477.1 1032.73  5712.9 1032.78  5913.2 1037.58
#Mann=6,-1,0
  4262.2    0.12       0  4881.6    0.05       0  4999.6    0.05       0
  5013.1    0.05       0  5313.8    0.12       0  5477.1    0.05       0
Bank Sta=4999.6,5013.1
Exp/Cntr=0.3,0.1

Type RM Length L Ch R = 1,22190,447,447,447
BEGIN DESCRIPTION:
MILLER CREEK 39.0
END DESCRIPTION:
XS GIS Cut Line= 3
      2867855.67     10257803.11      2867256.25     10257813.00
      2866255.70     10257903.11
#Sta/Elev= 30
  4400.5 1038.89  4430.5 1034.54  4445.1 1033.69  4520.5 1027.84  4620.5 1022.68
  4660.5 1023.44  4690.5 1022.66  4720.5 1023.61  4738.6 1023.21  4840.5 1024.93
  4880.5 1024.83  4960.6 1020.94  4970.6 1019.93  4990.6 1015.11  5013.9 1014.55
  5014.4 1014.05  5026.9 1014.05  5027.4 1014.55  5030.7 1017.60  5040.7 1021.14
  5050.8 1022.52  5151.2 1023.86  5214.7 1025.83  5331.9 1030.23  5432.8 1031.88
  5572.9 1032.82  5693.4 1032.32  5844.0 1032.72  5944.1 1035.73  6004.6 1036.75
#Mann=7,-1,0
  4400.5    0.05       0  4445.1    0.12       0  4738.6    0.05       0
  5013.9    0.03       0  5027.4    0.05       0  5214.7    0.12       0
  5432.8    0.05       0
Bank Sta=5013.9,5027.4
Exp/Cntr=0.3,0.1

Type RM Length L Ch R = 1,21743,489,489,489
BEGIN DESCRIPTION:
MILLER CREEK 38.0
END DESCRIPTION:
XS GIS Cut Line= 3
      2867905.66     10257753.10      2867435.75     10257405.00
      2866755.69     10257503.11
#Sta/Elev= 30
  4415.2 1043.44  4508.0 1035.29  4537.3 1031.13  4572.8 1027.73  4579.0 1028.26
  4608.2 1025.14  4637.5 1023.73  4643.7 1024.37  4658.3 1022.35  4743.9 1021.31
  4950.4 1023.43  4965.1 1019.62  4973.5 1015.09  4979.7 1014.03  4980.8 1012.85
  4981.3 1012.35  4994.4 1012.85  5030.4 1014.59  5040.5 1016.50  5050.6 1019.92
  5060.7 1021.11  5099.9 1021.46  5141.5 1020.61  5159.3 1022.38  5164.3 1021.64
  5181.9 1023.34  5200.3 1023.50  5271.3 1026.29  5450.9 1031.48  5687.1 1032.76
#Mann=7,-1,0
  4415.2    0.05       0  4980.8    0.03       0  4994.4    0.05       0
  5099.9    0.12       0  5200.3    0.05       0  5271.3    0.12       0
  5450.9    0.05       0
Bank Sta=4980.8,4994.4
Exp/Cntr=0.3,0.1

Type RM Length L Ch R = 1,21254,901,901,901
BEGIN DESCRIPTION:
MILLER CREEK 37.0
END DESCRIPTION:
XS GIS Cut Line= 3
      2868055.67     10257253.10      2867769.00     10257079.00
      2866255.69     10257103.11
#Sta/Elev= 30
  4664.6 1033.74  4723.1 1030.73  4735.9 1029.41  4889.4 1022.32  4910.8 1019.93
  4926.2 1016.43  4941.7 1018.71  4957.1 1018.83  4963.1 1016.03  4968.9 1016.02
  4980.2 1013.86  4984.4 1013.11  4985.3 1011.09  4985.8 1010.59  4999.0 1011.09
  5033.3 1012.14  5053.3 1015.85  5063.3 1016.06  5073.3 1017.62  5103.3 1017.72
  5193.3 1022.42  5253.3 1024.70  5303.4 1025.48  5393.4 1024.43  5513.4 1024.57
  5913.4 1029.52  5933.4 1030.30  6263.5 1031.44  6433.5 1031.16  6513.5 1033.06
#Mann=5,-1,0
  4664.6    0.05       0  4735.9    0.12       0  4980.2    0.05       0
  4985.3    0.05       0  4999.0    0.05       0
Bank Sta=4985.3,4999
Exp/Cntr=0.3,0.1

Type RM Length L Ch R = 1,20353,495,495,495
BEGIN DESCRIPTION:
MILLER CREEK 36.0
END DESCRIPTION:
XS GIS Cut Line= 3
      2869255.71     10255903.10      2868147.00     10256279.00
      2866655.65     10257053.13
#Sta/Elev= 30
  3829.3 1034.44  4159.1 1024.62  4399.5 1021.33  4507.1 1016.32  4536.8 1014.64
  4562.2 1010.88  4610.7 1014.42  4651.2 1010.00  4688.3 1008.01  4688.8 1007.51
  4702.0 1008.01  4705.7 1008.96  4714.0 1014.01  4719.3 1011.41  4726.9 1014.72
  4768.9 1016.32  4876.3 1017.04  4902.4 1015.17  4939.1 1015.79  4948.6 1015.33
  4965.3 1010.69  5024.7 1009.14  5041.2 1012.73  5080.4 1014.44  5201.8 1018.04
  5323.1 1017.57  5665.8 1022.29  6251.7 1024.85  6517.2 1029.39  6680.3 1030.73
#Mann=7,-1,0
  3829.3    0.12       0  4507.1    0.05       0  4688.3    0.05       0
  4702.0    0.05       0  4768.9    0.05       0  5080.4    0.12       0
  5201.8    0.05       0
Bank Sta=4688.3,4702
Exp/Cntr=0.3,0.1