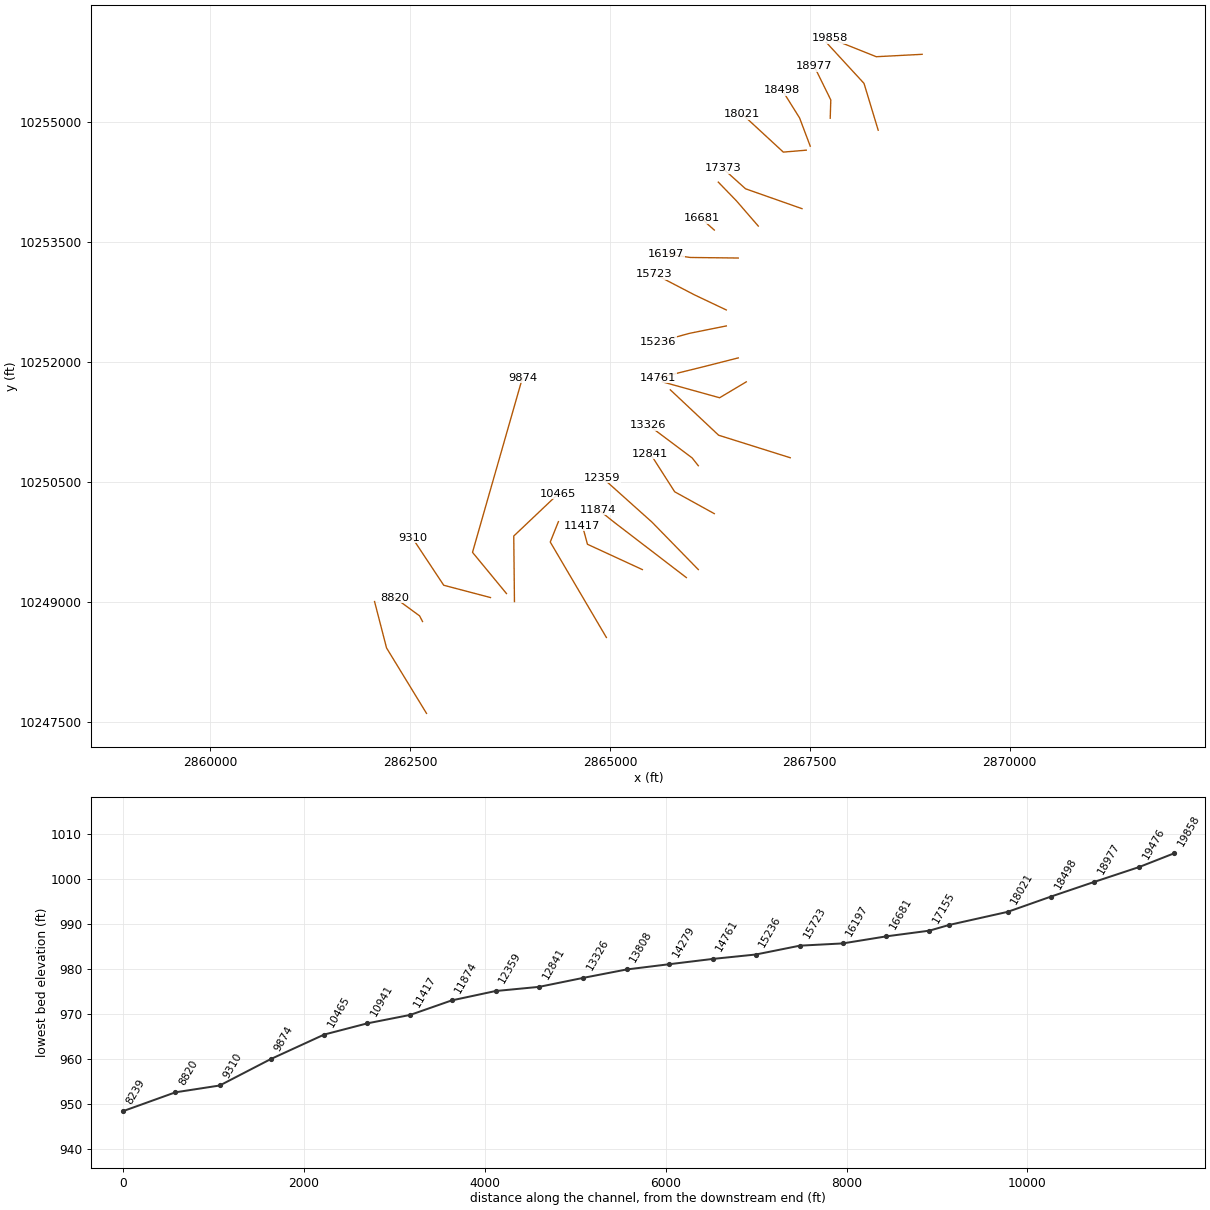
HEC-RAS study MILLER CREEK.prj: MILLER CREEK Base Level Engineering

--- MILLER CREEK.g01 (geometry) --- (continued)

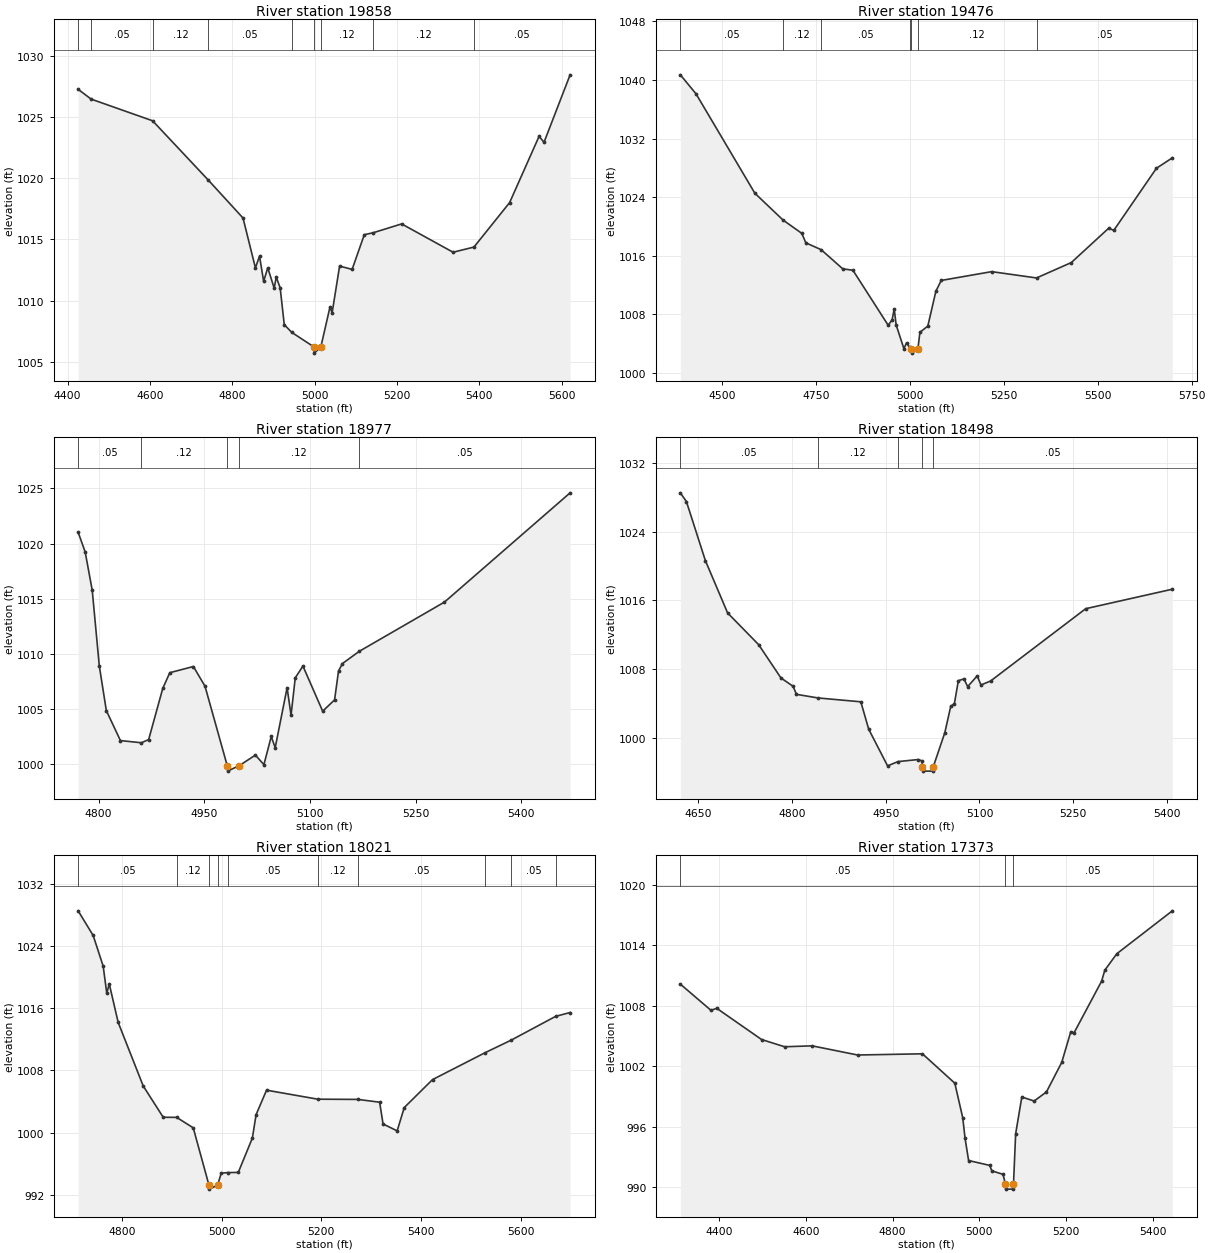
Type RM Length L Ch R = 1,19858,382,382,382
BEGIN DESCRIPTION:
MILLER CREEK 35.0
END DESCRIPTION:
XS GIS Cut Line= 3
      2868905.66     10255853.11      2868332.25     10255823.00
      2867755.67     10256053.12
#Sta/Elev= 30
  4425.8 1027.25  4457.3 1026.45  4606.7 1024.68  4741.8 1019.85  4826.3 1016.75
  4856.4 1012.68  4866.4 1013.64  4876.4 1011.58  4886.4 1012.69  4902.0 1011.03
  4907.0 1011.93  4916.5 1011.06  4926.5 1008.05  4944.8 1007.42  4998.9 1006.23
  4999.4 1005.73  5015.3 1006.23  5037.4 1009.47  5042.8 1009.03  5060.9 1012.83
  5091.3 1012.56  5120.9 1015.39  5142.5 1015.55  5211.6 1016.27  5336.5 1013.96
  5387.2 1014.38  5473.9 1018.01  5545.4 1023.41  5557.5 1022.93  5620.8 1028.43
#Mann=9,-1,0
  4425.8    0.12       0  4457.3    0.05       0  4606.7    0.12       0
  4741.8    0.05       0  4944.8    0.12       0  4998.9    0.07       0
  5015.3    0.12       0  5142.5    0.12       0  5387.2    0.05       0
Bank Sta=4998.9,5015.3
Exp/Cntr=0.3,0.1

Type RM Length L Ch R = 1,19476,499,499,499
BEGIN DESCRIPTION:
MILLER CREEK 34.0
END DESCRIPTION:
XS GIS Cut Line= 3
      2868355.69     10254903.11      2868178.50     10255489.00
      2867705.67     10256003.13
#Sta/Elev= 30
  4387.9 1040.69  4429.7 1038.09  4586.4 1024.53  4661.5 1020.87  4711.3 1019.06
  4722.2 1017.76  4762.9 1016.83  4820.6 1014.21  4847.6 1014.02  4941.6 1006.51
  4952.1 1007.27  4957.6 1008.75  4962.8 1006.55  4983.4 1003.32  4990.5 1004.12
  4998.8 1003.48  5003.4 1003.21  5003.9 1002.71  5020.5 1003.21  5026.1 1005.55
  5047.1 1006.40  5068.7 1011.17  5082.9 1012.63  5217.3 1013.83  5336.7 1012.97
  5429.4 1015.07  5528.6 1019.74  5542.8 1019.48  5656.2 1027.94  5698.5 1029.36
#Mann=7,-1,0
  4387.9    0.05       0  4661.5    0.12       0  4762.9    0.05       0
  4998.8    0.12       0  5003.4    0.07       0  5020.5    0.12       0
  5336.7    0.05       0
Bank Sta=5003.4,5020.5
Exp/Cntr=0.3,0.1

Type RM Length L Ch R = 1,18977,479,479,479
BEGIN DESCRIPTION:
MILLER CREEK 33.0
END DESCRIPTION:
XS GIS Cut Line= 3
      2867755.68     10255053.11      2867762.75     10255282.00
      2867555.67     10255703.14
#Sta/Elev= 30
  4771.0 1021.03  4781.0 1019.24  4791.0 1015.77  4801.0 1008.93  4811.0 1004.87
  4831.0 1002.15  4860.8 1001.95  4871.1 1002.24  4891.1 1006.87  4901.1 1008.30
  4934.6 1008.86  4951.1 1007.07  4982.6  999.88  4983.1  999.38  4999.7  999.88
  5022.6 1000.83  5034.7  999.97  5045.1 1002.52  5050.7 1001.50  5067.6 1006.94
  5073.2 1004.45  5079.2 1007.84  5090.1 1008.90  5118.1 1004.81  5135.0 1005.84
  5140.6 1008.46  5146.2 1009.13  5170.1 1010.24  5291.0 1014.70  5469.3 1024.60
#Mann=5,-1,0
  4771.0    0.05       0  4860.8    0.12       0  4982.6    0.07       0
  4999.7    0.12       0  5170.1    0.05       0
Bank Sta=4982.6,4999.7
Exp/Cntr=0.3,0.1

Type RM Length L Ch R = 1,18498,477,477,477
BEGIN DESCRIPTION:
MILLER CREEK 32.0
END DESCRIPTION:
XS GIS Cut Line= 3
      2867505.68     10254703.12      2867372.25     10255057.00
      2867155.67     10255403.13
#Sta/Elev= 30
  4621.8 1028.51  4631.5 1027.49  4661.8 1020.62  4697.3 1014.53  4747.0 1010.83
  4782.6 1006.96  4802.1 1005.98  4807.4 1005.05  4841.9 1004.63  4910.3 1004.18
  4922.9 1000.99  4953.1  996.72  4969.7  997.22  5002.1  997.46  5008.0  997.30
  5008.9  996.61  5009.4  996.11  5025.6  996.11  5026.1  996.61  5044.6 1000.59
  5054.0 1003.64  5059.9 1003.97  5066.2 1006.64  5075.2 1006.85  5081.1 1005.95
  5096.4 1007.20  5102.3 1006.14  5117.7 1006.60  5269.8 1015.02  5408.3 1017.29
#Mann=5,-1,0
  4621.8    0.05       0  4841.9    0.12       0  4969.7    0.05       0
  5008.9    0.05       0  5026.1    0.05       0
Bank Sta=5008.9,5026.1
Exp/Cntr=0.3,0.1

Type RM Length L Ch R = 1,18021,648,648,648
BEGIN DESCRIPTION:
MILLER CREEK 31.0
END DESCRIPTION:
XS GIS Cut Line= 3
      2867455.69     10254653.11      2867169.00     10254629.00
      2866655.66     10255103.13
#Sta/Elev= 30
  4712.3 1028.55  4742.4 1025.38  4762.5 1021.43  4769.7 1017.95  4774.7 1019.14
  4792.6 1014.18  4842.8 1006.00  4882.9 1001.97  4909.8 1001.96  4943.1 1000.61
  4974.7  993.22  4975.2  992.72  4991.9  993.22  4999.2  994.77  5012.1  994.85
  5033.4  994.87  5061.7  999.30  5069.1 1002.30  5090.1 1005.46  5192.8 1004.30
  5273.3 1004.27  5316.9 1003.91  5323.7 1001.11  5352.0 1000.22  5366.2 1003.22
  5422.9 1006.82  5528.8 1010.30  5580.9 1011.91  5669.7 1014.96  5698.8 1015.46
#Mann=10,-1,0
  4712.3    0.05       0  4909.8    0.12       0  4974.7    0.07       0
  4991.9    0.12       0  5012.1    0.05       0  5192.8    0.12       0
  5273.3    0.05       0  5528.8    0.12       0  5580.9    0.05       0
  5669.7    0.12       0
Bank Sta=4974.7,4991.9
Exp/Cntr=0.3,0.1

Type RM Length L Ch R = 1,17373,218,218,218
BEGIN DESCRIPTION:
MILLER CREEK 30.0
END DESCRIPTION:
XS GIS Cut Line= 3
      2867402.19     10253921.14      2866696.62     10254169.70
      2866410.07     10254427.62
#Sta/Elev= 30
  4311.0 1010.16  4381.5 1007.56  4394.8 1007.76  4498.1 1004.66  4551.1 1003.94
  4614.8 1004.03  4719.4 1003.12  4868.8 1003.24  4943.4 1000.32  4961.7  996.88
  4967.0  994.85  4975.2  992.64  5023.6  992.16  5028.9  991.61  5054.5  991.27
  5060.0  990.30  5060.5  989.80  5078.1  989.80  5078.6  990.30  5083.6  995.30
  5097.8  998.95  5126.2  998.55  5154.5  999.45  5189.7 1002.38  5210.6 1005.43
  5218.1 1005.32  5281.6 1010.45  5289.1 1011.55  5316.7 1013.18  5444.6 1017.44
#Mann=3,-1,0
  4311.0    0.05       0  5060.0    0.05       0  5078.6    0.05       0
Bank Sta=5060,5078.6
Exp/Cntr=0.3,0.1

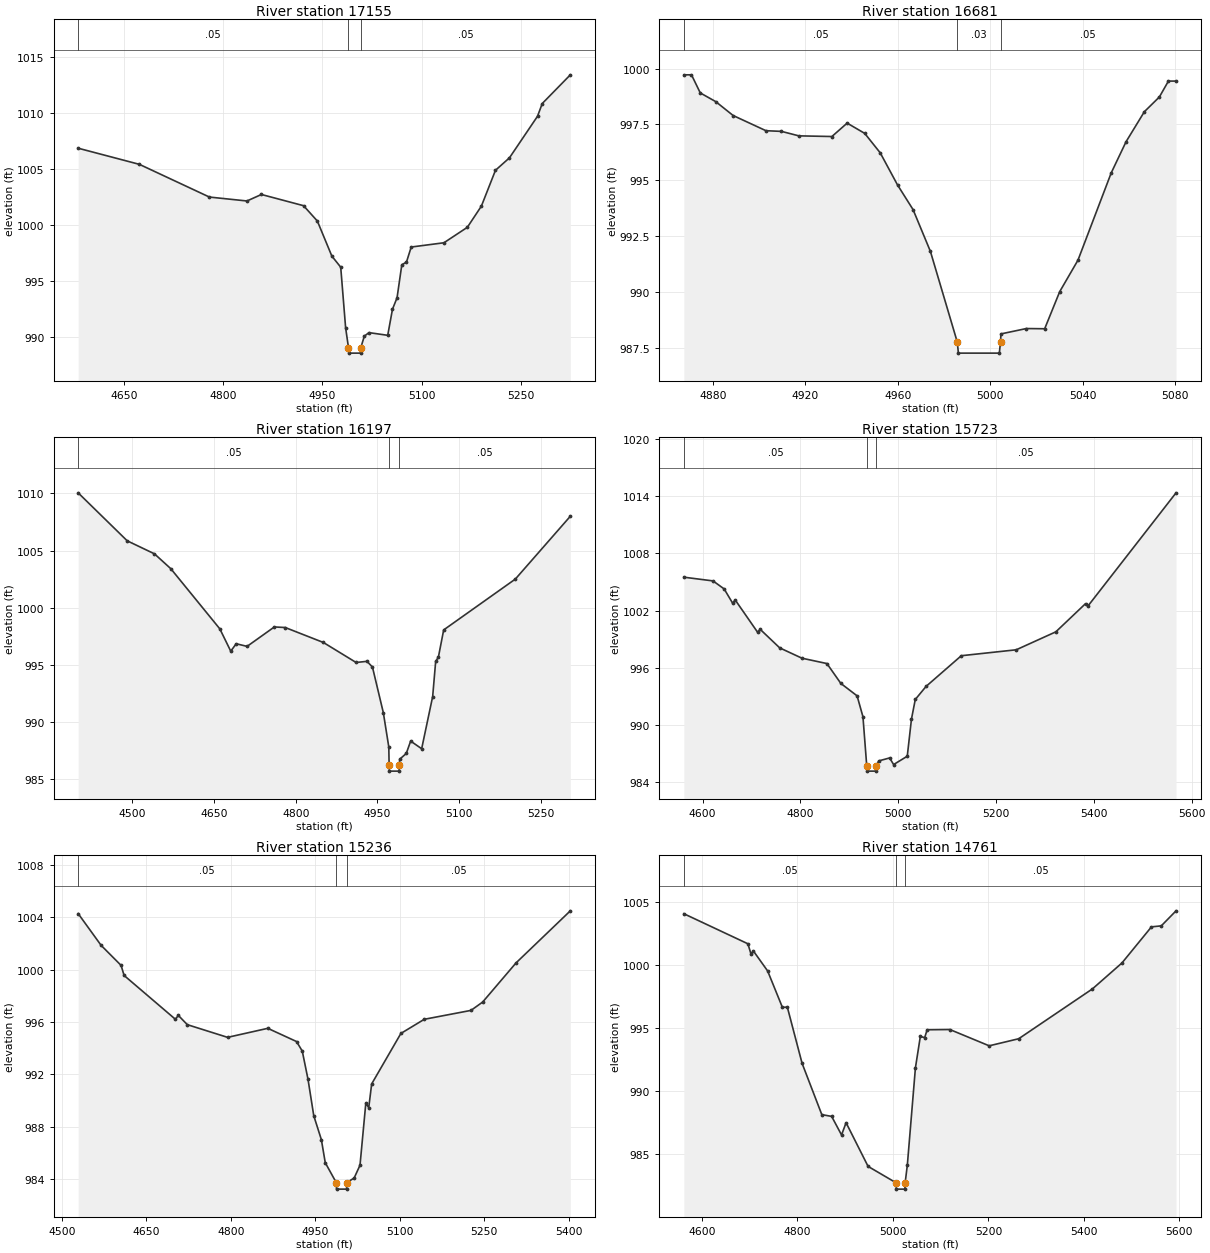
Type RM Length L Ch R = 1,17155,474,474,474
BEGIN DESCRIPTION:
MILLER CREEK 29.0
END DESCRIPTION:
XS GIS Cut Line= 3
      2866855.66     10253703.14      2866581.50     10254020.00
      2866355.65     10254253.15
#Sta/Elev= 30
  4581.0 1006.82  4673.5 1005.38  4779.3 1002.46  4836.0 1002.11  4857.9 1002.69
  4921.5 1001.69  4942.4 1000.32  4964.3  997.19  4977.7  996.20  4985.1  990.79
  4989.4  989.03  4989.9  988.53  5007.6  988.53  5008.1  989.03  5013.4  990.05
  5020.4  990.36  5048.7  990.12  5055.9  992.45  5062.8  993.47  5070.0  996.42
  5077.0  996.65  5084.2  998.00  5133.6  998.38  5169.0  999.76  5190.2 1001.65
  5211.5 1004.85  5232.6 1005.96  5275.0 1009.67  5282.2 1010.81  5324.6 1013.37
#Mann=3,-1,0
  4581.0    0.05       0  4989.4    0.05       0  5008.1    0.05       0
Bank Sta=4989.4,5008.1
Exp/Cntr=0.3,0.1

Type RM Length L Ch R = 1,16681,484,484,484
BEGIN DESCRIPTION:
MILLER CREEK 28.0
END DESCRIPTION:
XS GIS Cut Line= 3
      2866305.67     10253653.13      2866206.50     10253741.00
      2866155.65     10253803.15
#Sta/Elev= 30
  4867.5  999.72  4870.8  999.72  4874.6  998.91  4881.3  998.52  4888.8  997.90
  4903.0  997.22  4909.7  997.19  4917.2  996.99  4931.5  996.96  4938.1  997.56
  4945.7  997.10  4952.4  996.23  4959.9  994.79  4966.6  993.69  4974.1  991.82
  4985.7  987.77  4986.2  987.27  5003.9  987.27  5004.4  987.77  5004.6  988.13
  5015.6  988.37  5023.5  988.36  5030.0  990.02  5037.9  991.43  5052.3  995.34
  5058.7  996.73  5066.6  998.07  5073.1  998.73  5077.0  999.44  5080.3  999.44
#Mann=3,-1,0
  4867.5    0.05       0  4985.7    0.03       0  5004.4    0.05       0
Bank Sta=4985.7,5004.4
Exp/Cntr=0.3,0.1

Type RM Length L Ch R = 1,16197,474,474,474
BEGIN DESCRIPTION:
MILLER CREEK 27.0
END DESCRIPTION:
XS GIS Cut Line= 3
      2866605.66     10253303.11      2866006.50     10253310.00
      2865705.67     10253353.11
#Sta/Elev= 30
  4400.8 1010.05  4490.8 1005.85  4540.8 1004.71  4570.8 1003.41  4660.8  998.14
  4680.8  996.19  4690.8  996.84  4710.8  996.61  4760.8  998.31  4780.8  998.26
  4850.8  996.95  4910.8  995.20  4930.8  995.30  4940.8  994.80  4960.8  990.80
  4970.8  987.80  4971.4  986.19  4971.9  985.69  4989.7  985.69  4990.2  986.19
  4990.8  986.73  5002.9  987.24  5010.9  988.32  5031.1  987.65  5051.3  992.22
  5056.8  995.29  5061.8  995.67  5071.5  998.05  5203.0 1002.50  5303.9 1008.00
#Mann=3,-1,0
  4400.8    0.05       0  4971.4    0.03       0  4990.2    0.05       0
Bank Sta=4971.4,4990.2
Exp/Cntr=0.3,0.1

Type RM Length L Ch R = 1,15723,487,487,487
BEGIN DESCRIPTION:
MILLER CREEK 26.0
END DESCRIPTION:
XS GIS Cut Line= 3
      2866455.73     10252653.09      2866059.75     10252841.00
      2865555.72     10253103.09
#Sta/Elev= 30
  4561.7 1005.49  4621.3 1005.10  4644.1 1004.26  4661.3 1002.78  4666.8 1003.10
  4712.3  999.74  4717.8 1000.03  4757.7  998.09  4803.2  997.01  4854.2  996.45
  4882.7  994.37  4915.9  993.07  4927.9  990.88  4935.7  985.69  4936.2  985.19
  4954.0  985.19  4954.5  985.69  4960.2  986.26  4982.4  986.57  4990.6  985.88
  5018.5  986.75  5027.1  990.64  5034.9  992.69  5057.0  994.06  5129.0  997.27
  5241.3  997.89  5322.3  999.77  5383.0 1002.72  5388.7 1002.52  5568.1 1014.32
#Mann=3,-1,0
  4561.7    0.05       0  4935.7    0.05       0  4954.5    0.05       0
Bank Sta=4935.7,4954.5
Exp/Cntr=0.3,0.1

Type RM Length L Ch R = 1,15236,475,475,475
BEGIN DESCRIPTION:
MILLER CREEK 25.0
END DESCRIPTION:
XS GIS Cut Line= 3
      2866455.70     10252453.12      2865994.00     10252360.00
      2865605.64     10252253.10
#Sta/Elev= 30
  4529.0 1004.28  4569.8 1001.85  4605.2 1000.32  4610.6  999.55  4701.7  996.20
  4706.8  996.50  4722.8  995.79  4794.3  994.82  4865.7  995.51  4916.7  994.50
  4926.9  993.77  4937.1  991.61  4947.3  988.83  4960.8  987.00  4967.7  985.24
  4987.2  983.72  4987.7  983.22  5005.5  983.22  5006.0  983.72  5019.0  984.07
  5029.4  985.05  5039.7  989.79  5044.9  989.45  5050.1  991.26  5102.0  995.12
  5143.5  996.20  5226.4  996.88  5247.2  997.52  5306.4 1000.51  5402.8 1004.49
#Mann=3,-1,0
  4529.0    0.05       0  4987.2    0.03       0  5006.0    0.05       0
Bank Sta=4987.2,5006
Exp/Cntr=0.3,0.1

Type RM Length L Ch R = 1,14761,482,482,482
BEGIN DESCRIPTION:
MILLER CREEK 24.0
END DESCRIPTION:
XS GIS Cut Line= 3
      2866605.64     10252053.10      2866181.50     10251945.00
      2865605.72     10251803.12
#Sta/Elev= 30
  4562.3 1004.05  4696.4 1001.67  4702.8 1000.87  4707.9 1001.10  4737.7  999.52
  4768.6  996.64  4779.0  996.65  4809.9  992.20  4851.2  988.14  4871.8  988.00
  4892.5  986.53  4902.0  987.50  4948.1  984.04  5006.8  982.74  5007.3  982.24
  5025.2  982.24  5025.7  982.74  5030.3  984.15  5047.2  991.84  5057.5  994.33
  5066.6  994.24  5071.8  994.86  5119.3  994.88  5201.7  993.59  5263.5  994.15
  5418.0  998.10  5479.7 1000.15  5541.5 1003.01  5562.1 1003.09  5593.0 1004.28
#Mann=3,-1,0
  4562.3    0.05       0  5006.8    0.03       0  5025.7    0.05       0
Bank Sta=5006.8,5025.7
Exp/Cntr=0.3,0.1

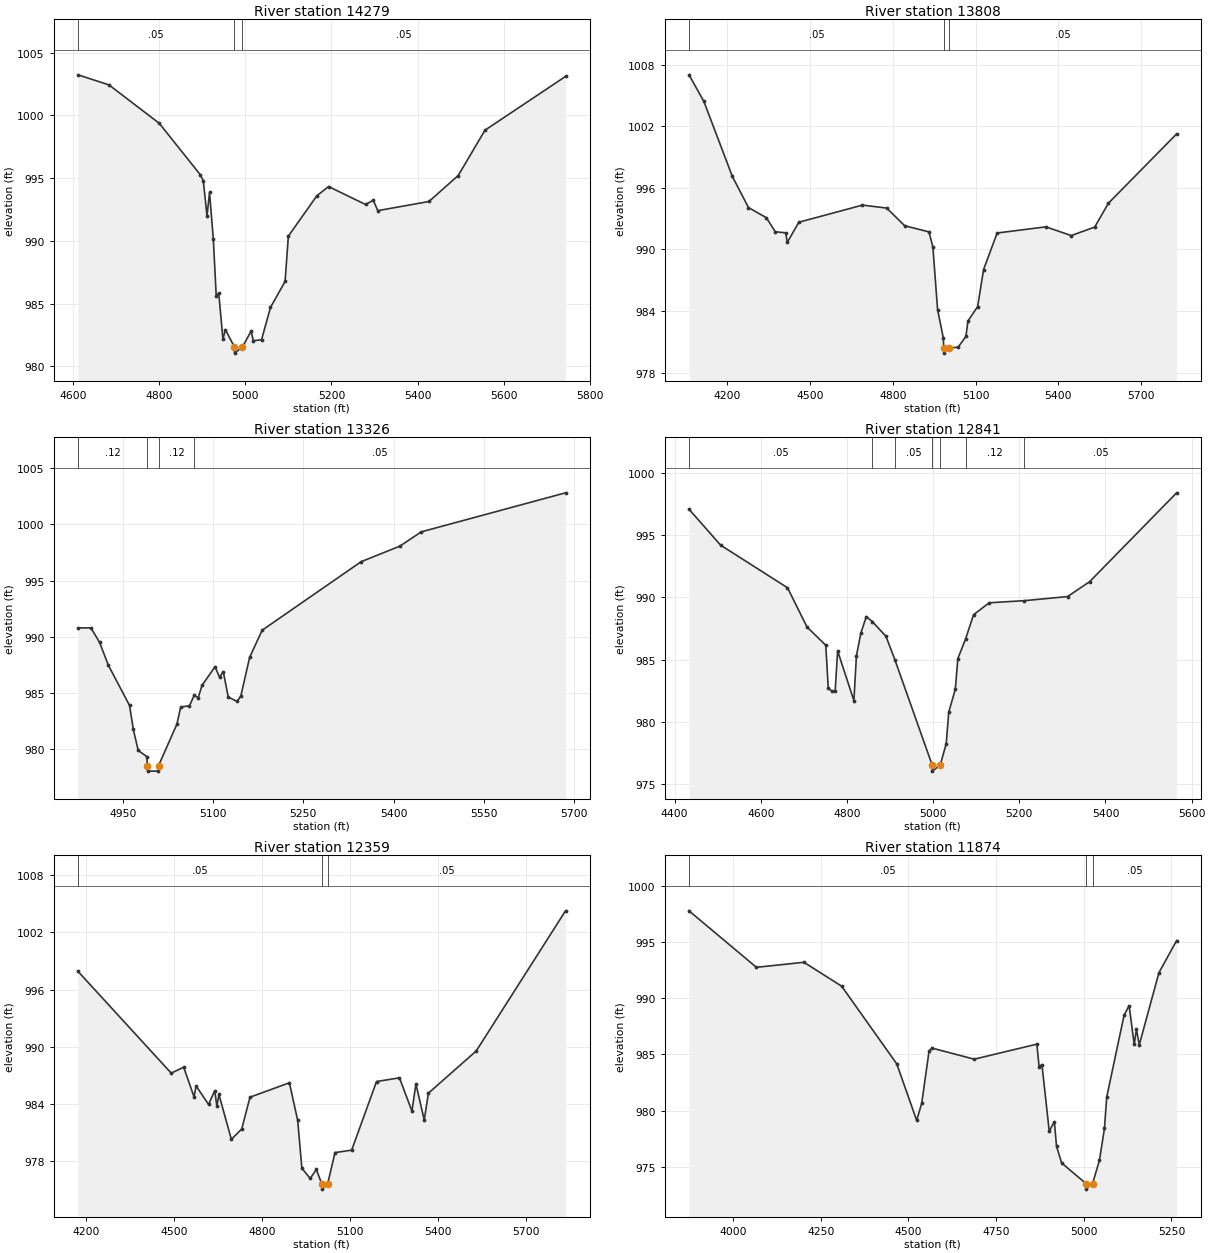
Type RM Length L Ch R = 1,14279,471,471,471
BEGIN DESCRIPTION:
MILLER CREEK 23.0
END DESCRIPTION:
XS GIS Cut Line= 3
      2866705.71     10251753.12      2866372.00     10251554.00
      2865655.66     10251753.12
#Sta/Elev= 30
  4611.4 1003.23  4683.4 1002.43  4800.2  999.37  4895.6  995.27  4902.5  994.79
  4911.1  992.00  4917.0  993.86  4925.8  990.14  4932.5  985.64  4938.4  985.83
  4948.1  982.17  4953.9  982.93  4974.6  981.56  4975.1  981.06  4993.5  981.56
  5013.5  982.81  5018.7  982.05  5037.7  982.12  5058.5  984.70  5092.4  986.77
  5100.0  990.38  5166.1  993.59  5193.4  994.33  5279.2  992.90  5297.2  993.24
  5307.6  992.41  5426.5  993.14  5494.4  995.21  5556.6  998.82  5743.5 1003.10
#Mann=3,-1,0
  4611.4    0.05       0  4974.6    0.03       0  4993.5    0.05       0
Bank Sta=4974.6,4993.5
Exp/Cntr=0.3,0.1

Type RM Length L Ch R = 1,13808,482,482,482
BEGIN DESCRIPTION:
MILLER CREEK 22.0
END DESCRIPTION:
XS GIS Cut Line= 3
      2867255.65     10250803.12      2866359.75     10251085.00
      2865755.72     10251653.08
#Sta/Elev= 30
  4060.8 1007.02  4114.6 1004.43  4218.0  997.11  4276.5  994.08  4341.3  993.09
  4373.7  991.72  4411.3  991.62  4417.2  990.69  4459.1  992.65  4689.8  994.32
  4778.0  994.03  4842.8  992.31  4930.9  991.71  4945.2  990.24  4962.3  984.13
  4983.3  981.34  4984.3  980.39  4984.8  979.89  5003.2  980.39  5036.8  980.47
  5065.1  981.52  5072.4  983.02  5107.6  984.43  5129.1  988.04  5178.4  991.60
  5355.2  992.20  5447.1  991.35  5532.1  992.18  5581.8  994.50  5829.2 1001.26
#Mann=3,-1,0
  4060.8    0.05       0  4984.3    0.03       0  5003.2    0.05       0
Bank Sta=4984.3,5003.2
Exp/Cntr=0.3,0.1

Type RM Length L Ch R = 1,13326,485,485,485
BEGIN DESCRIPTION:
MILLER CREEK 21.0
END DESCRIPTION:
XS GIS Cut Line= 3
      2866105.68     10250703.12      2866028.25     10250801.00
      2865479.56     10251212.57
#Sta/Elev= 30
  4875.2  990.78  4896.8  990.78  4911.3  989.48  4925.7  987.46  4961.0  983.87
  4967.3  981.74  4975.4  979.86  4989.8  979.30  4990.5  978.51  4991.0  978.01
  5008.9  978.01  5009.4  978.51  5039.8  982.20  5046.1  983.72  5060.7  983.84
  5068.6  984.77  5075.2  984.55  5081.5  985.65  5103.2  987.32  5110.7  986.38
  5116.9  986.88  5125.2  984.61  5139.8  984.23  5146.1  984.71  5160.7  988.15
  5181.5  990.57  5346.1  996.68  5410.6  998.07  5446.1  999.34  5685.9 1002.82
#Mann=4,-1,0
  4875.2    0.12       0  4990.5    0.07       0  5009.4    0.12       0
  5068.6    0.05       0
Bank Sta=4990.5,5009.4
Exp/Cntr=0.3,0.1

Type RM Length L Ch R = 1,12841,482,482,482
BEGIN DESCRIPTION:
MILLER CREEK 20.0
END DESCRIPTION:
XS GIS Cut Line= 3
      2866305.67     10250103.12      2865810.00     10250377.00
      2865505.66     10250853.15
#Sta/Elev= 30
  4433.7  997.10  4507.0  994.21  4662.2  990.78  4707.5  987.62  4751.0  986.15
  4756.7  982.74  4765.0  982.44  4772.8  982.47  4778.5  985.70  4816.3  981.69
  4822.1  985.29  4832.4  987.13  4845.0  988.45  4858.9  988.06  4890.7  986.87
  4911.2  985.00  4997.8  976.52  4998.3  976.02  5016.7  976.52  5030.5  978.23
  5036.4  980.77  5051.6  982.61  5057.5  985.08  5075.3  986.64  5093.9  988.61
  5130.3  989.57  5211.5  989.74  5312.1  990.07  5363.3  991.27  5565.1  998.42
#Mann=7,-1,0
  4433.7    0.05       0  4858.9    0.12       0  4911.2    0.05       0
  4997.8    0.05       0  5016.7    0.05       0  5075.3    0.12       0
  5211.5    0.05       0
Bank Sta=4997.8,5016.7
Exp/Cntr=0.3,0.1

Type RM Length L Ch R = 1,12359,485,485,485
BEGIN DESCRIPTION:
MILLER CREEK 19.0
END DESCRIPTION:
XS GIS Cut Line= 3
      2866105.68     10249403.11      2865528.25     10249995.00
      2864905.69     10250553.11
#Sta/Elev= 30
  4173.1  997.93  4491.4  987.25  4533.8  987.87  4569.1  984.77  4576.2  985.91
  4618.7  983.97  4639.8  985.41  4647.0  983.78  4654.0  985.02  4696.4  980.31
  4731.8  981.40  4760.0  984.73  4894.4  986.24  4922.7  982.29  4936.9  977.28
  4965.2  976.21  4986.3  977.15  5005.5  975.59  5006.0  975.09  5024.4  975.59
  5050.0  978.92  5106.8  979.18  5191.5  986.37  5269.8  986.76  5312.3  983.27
  5325.9  986.12  5354.3  982.33  5368.5  985.15  5531.5  989.57  5836.1 1004.27
#Mann=3,-1,0
  4173.1    0.05       0  5005.5    0.05       0  5024.4    0.05       0
Bank Sta=5005.5,5024.4
Exp/Cntr=0.3,0.1

Type RM Length L Ch R = 1,11874,457,457,457
BEGIN DESCRIPTION:
MILLER CREEK 18.0
END DESCRIPTION:
XS GIS Cut Line= 3
      2865955.65     10249303.14      2865062.75     10249988.00
      2864855.71     10250153.09
#Sta/Elev= 30
  3874.7  997.78  4066.8  992.75  4202.3  993.20  4309.8  991.07  4467.0  984.15
  4523.7  979.12  4538.2  980.66  4559.0  985.29  4567.2  985.56  4687.8  984.57
  4866.4  985.91  4872.7  983.91  4880.9  984.08  4901.7  978.15  4916.2  979.01
  4922.5  976.81  4937.0  975.33  5006.3  973.50  5006.8  973.00  5025.3  973.50
  5044.7  975.55  5059.1  978.40  5065.5  981.19  5115.1  988.49  5129.5  989.34
  5143.9  985.89  5150.3  987.24  5158.3  985.84  5214.4  992.27  5264.8  995.13
#Mann=3,-1,0
  3874.7    0.05       0  5006.3    0.05       0  5025.3    0.05       0
Bank Sta=5006.3,5025.3
Exp/Cntr=0.3,0.1

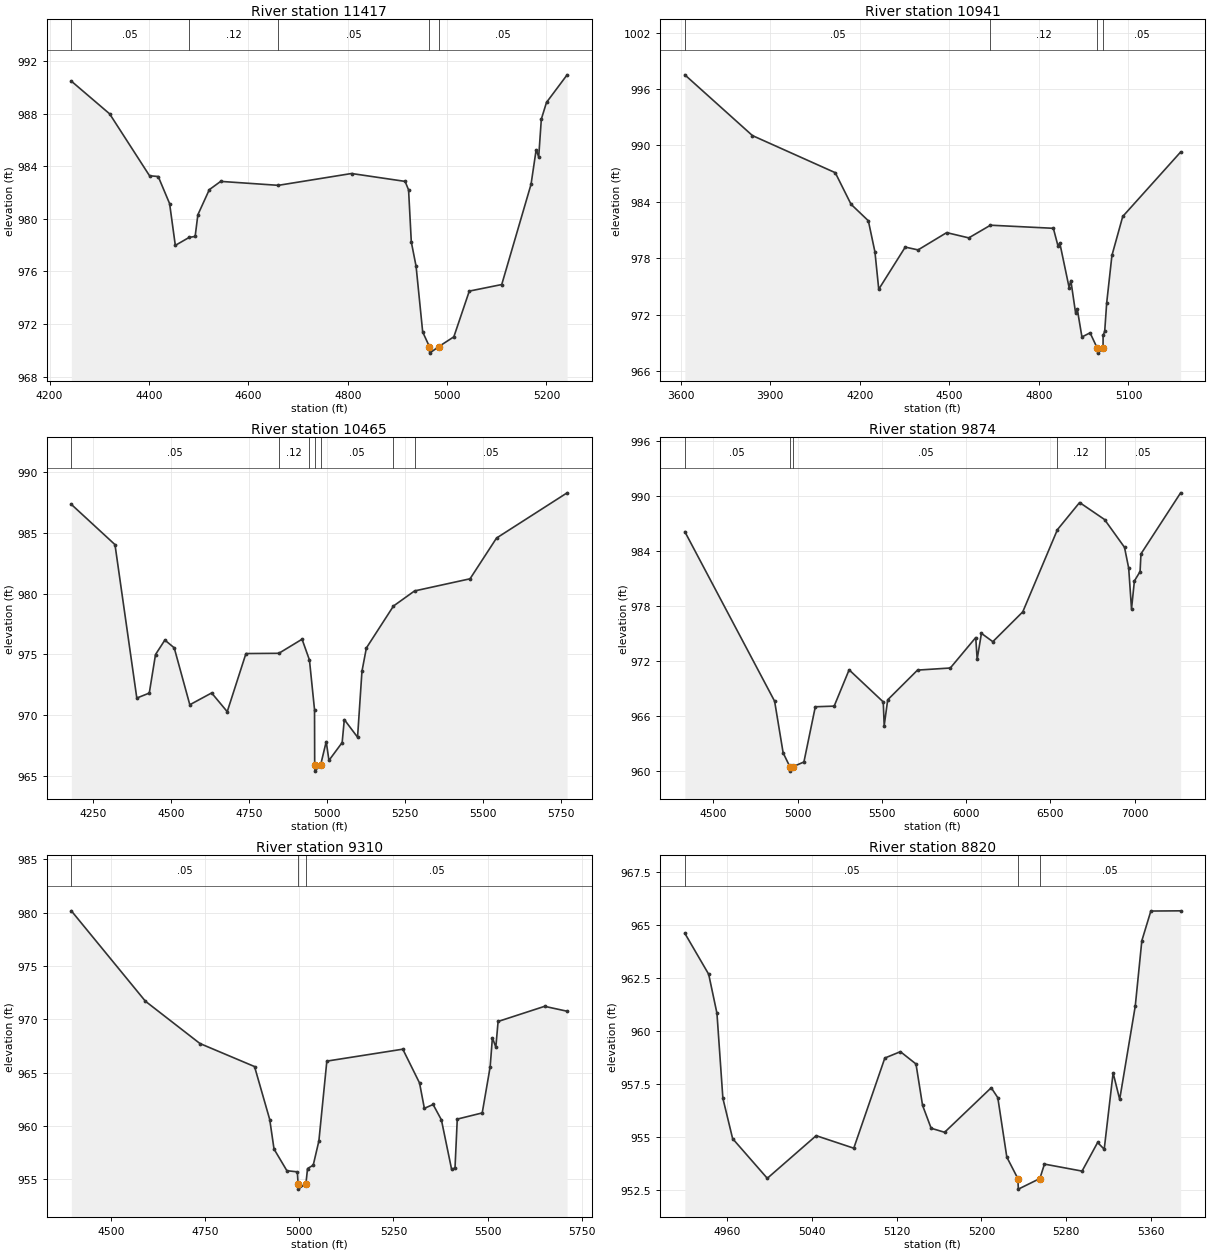
Type RM Length L Ch R = 1,11417,476,476,476
BEGIN DESCRIPTION:
MILLER CREEK 17.0
END DESCRIPTION:
XS GIS Cut Line= 3
      2865405.71     10249403.10      2864719.00     10249720.00
      2864655.67     10249953.15
#Sta/Elev= 30
  4243.7  990.48  4320.8  987.99  4401.1  983.28  4418.6  983.22  4441.5  981.16
  4453.0  977.98  4481.0  978.59  4492.9  978.66  4498.4  980.31  4521.4  982.22
  4544.3  982.85  4660.3  982.55  4807.7  983.45  4915.5  982.85  4922.5  982.20
  4928.0  978.24  4937.6  976.39  4950.9  971.39  4964.4  970.28  4964.9  969.78
  4983.4  970.28  5013.6  971.02  5044.7  974.50  5110.0  975.00  5169.0  982.63
  5179.3  985.26  5184.4  984.71  5189.7  987.59  5200.1  988.86  5241.6  990.96
#Mann=5,-1,0
  4243.7    0.05       0  4481.0    0.12       0  4660.3    0.05       0
  4964.4    0.05       0  4983.4    0.05       0
Bank Sta=4964.4,4983.4
Exp/Cntr=0.3,0.1

Type RM Length L Ch R = 1,10941,476,476,476
BEGIN DESCRIPTION:
MILLER CREEK 16.0
END DESCRIPTION:
XS GIS Cut Line= 3
      2864955.67     10248553.14      2864253.50     10249748.00
      2864355.68     10250003.10
#Sta/Elev= 30
  3614.1  997.52  3840.6  991.05  4118.0  987.10  4170.8  983.74  4228.8  981.98
  4250.9  978.66  4263.6  974.69  4352.4  979.18  4395.3  978.88  4491.1  980.72
  4565.2  980.16  4637.9  981.51  4848.5  981.18  4864.2  979.28  4870.0  979.62
  4901.3  974.87  4907.1  975.62  4922.8  972.20  4928.6  972.58  4944.2  969.61
  4971.5  970.05  4996.0  968.39  4996.5  967.89  5015.0  968.39  5015.1  969.78
  5020.5  970.21  5027.1  973.22  5044.7  978.29  5080.9  982.44  5274.8  989.30
#Mann=4,-1,0
  3614.1    0.05       0  4637.9    0.12       0  4996.0    0.07       0
  5015.0    0.05       0
Bank Sta=4996,5015
Exp/Cntr=0.3,0.1

Type RM Length L Ch R = 1,10465,591,591,591
BEGIN DESCRIPTION:
MILLER CREEK 15.0
END DESCRIPTION:
XS GIS Cut Line= 3
      2863805.68     10249003.15      2863797.00     10249823.00
      2864355.71     10250353.14
#Sta/Elev= 30
  4180.1  987.34  4320.1  984.03  4390.1  971.41  4430.1  971.82  4450.1  974.99
  4480.1  976.18  4510.1  975.54  4560.1  970.86  4630.1  971.83  4680.1  970.29
  4740.1  975.07  4845.6  975.09  4920.1  976.25  4943.8  974.54  4960.1  970.45
  4960.6  965.90  4961.1  965.40  4979.6  965.90  4997.6  967.83  5006.3  966.28
  5048.7  967.75  5055.6  969.64  5098.1  968.19  5112.2  973.61  5126.4  975.53
  5213.3  978.98  5280.9  980.22  5458.9  981.22  5543.8  984.57  5770.2  988.29
#Mann=7,-1,0
  4180.1    0.05       0  4845.6    0.12       0  4943.8    0.05       0
  4960.6    0.05       0  4979.6    0.05       0  5213.3    0.12       0
  5280.9    0.05       0
Bank Sta=4960.6,4979.6
Exp/Cntr=0.3,0.1

Type RM Length L Ch R = 1,9874,564,564,564
BEGIN DESCRIPTION:
MILLER CREEK 14.0
END DESCRIPTION:
XS GIS Cut Line= 3
      2863705.68     10249103.12      2863281.00     10249619.00
      2863905.69     10251803.12
#Sta/Elev= 30
  4331.8  986.13  4864.1  967.59  4914.7  961.94  4954.1  960.44  4954.6  959.94
  4974.9  960.44  5037.9  960.94  5105.5  966.98  5217.3  967.05  5305.9  971.02
  5508.3  967.51  5513.9  964.91  5534.7  967.74  5711.5  970.99  5906.0  971.22
  6056.7  974.55  6065.2  972.19  6090.5  975.01  6158.1  974.10  6335.6  977.36
  6541.1  986.35  6672.6  989.32  6820.6  987.46  6938.9  984.42  6963.7  982.15
  6980.5  977.68  6997.5  980.74  7031.3  981.77  7036.5  983.70  7271.7  990.38
#Mann=5,-1,0
  4331.8    0.05       0  4954.1    0.05       0  4974.9    0.05       0
  6541.1    0.12       0  6820.6    0.05       0
Bank Sta=4954.1,4974.9
Exp/Cntr=0.3,0.1

Type RM Length L Ch R = 1,9310,490,490,490
BEGIN DESCRIPTION:
MILLER CREEK 13.0
END DESCRIPTION:
XS GIS Cut Line= 3
      2863505.69     10249053.11      2862921.00     10249207.00
      2862528.81     10249799.57
#Sta/Elev= 30
  4395.4  980.17  4591.9  971.69  4736.6  967.72  4881.4  965.56  4921.7  960.59
  4933.1  957.82  4967.2  955.79  4995.0  955.68  4996.9  954.56  4997.4  954.06
  5017.7  954.56  5022.0  955.99  5037.1  956.31  5052.1  958.58  5073.2  966.07
  5274.7  967.19  5319.1  964.02  5331.9  961.64  5355.1  962.00  5377.1  960.56
  5404.1  955.93  5413.2  956.04  5419.2  960.63  5485.4  961.21  5506.4  965.52
  5512.4  968.26  5521.5  967.38  5527.5  969.79  5650.9  971.21  5710.6  970.75
#Mann=3,-1,0
  4395.4    0.05       0  4996.9    0.05       0  5017.7    0.05       0
Bank Sta=4996.9,5017.7
Exp/Cntr=0.3,0.1

Type RM Length L Ch R = 1,8820,581,581,581
BEGIN DESCRIPTION:
MILLER CREEK 12.0
END DESCRIPTION:
XS GIS Cut Line= 3
      2862655.67     10248753.14      2862618.75     10248824.00
      2862305.72     10249053.08
#Sta/Elev= 30
  4920.1  964.60  4942.6  962.67  4950.4  960.83  4956.0  956.82  4965.2  954.92
  4997.9  953.05  5044.0  955.06  5079.5  954.47  5108.8  958.72  5123.5  959.02
  5138.2  958.44  5144.4  956.49  5152.5  955.41  5165.2  955.22  5209.2  957.32
  5215.4  956.85  5223.9  954.05  5234.3  953.04  5234.8  952.54  5255.1  953.04
  5259.4  953.72  5294.9  953.39  5309.6  954.74  5315.8  954.42  5324.2  958.02
  5330.4  956.77  5345.1  961.17  5351.3  964.25  5359.8  965.65  5387.9  965.66
#Mann=3,-1,0
  4920.1    0.05       0  5234.3    0.05       0  5255.1    0.05       0
Bank Sta=5234.3,5255.1
Exp/Cntr=0.3,0.1

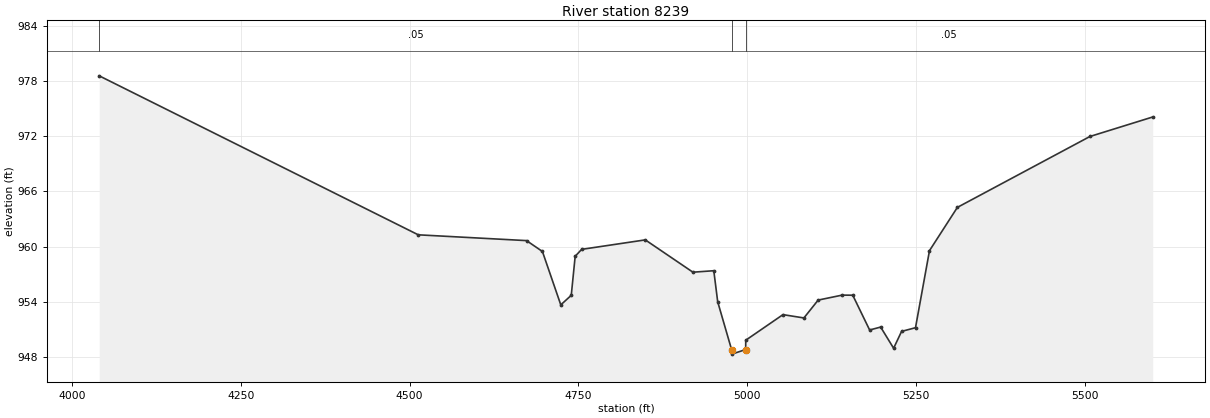
Type RM Length L Ch R = 1,8239,596,596,596
BEGIN DESCRIPTION:
MILLER CREEK 11.0
END DESCRIPTION:
XS GIS Cut Line= 3
      2862705.67     10247603.14      2862205.75     10248422.00
      2862055.68     10249003.14
#Sta/Elev= 30
  4040.6  978.56  4512.9  961.29  4673.2  960.66  4696.7  959.48  4723.9  953.68
  4739.4  954.72  4745.2  958.96  4754.8  959.71  4849.0  960.74  4919.5  957.23
  4950.4  957.39  4956.2  954.01  4976.7  948.83  4977.2  948.33  4997.6  948.83
  4997.7  949.84  5052.8  952.62  5083.8  952.26  5104.9  954.20  5140.4  954.74
  5156.1  954.73  5181.1  950.95  5197.4  951.27  5216.6  948.97  5228.4  950.80
  5249.0  951.20  5269.7  959.57  5311.0  964.27  5507.2  971.97  5600.2  974.09
#Mann=3,-1,0
  4040.6    0.05       0  4976.7    0.05       0  4997.6    0.05       0
Bank Sta=4976.7,4997.6
Exp/Cntr=0.3,0.1