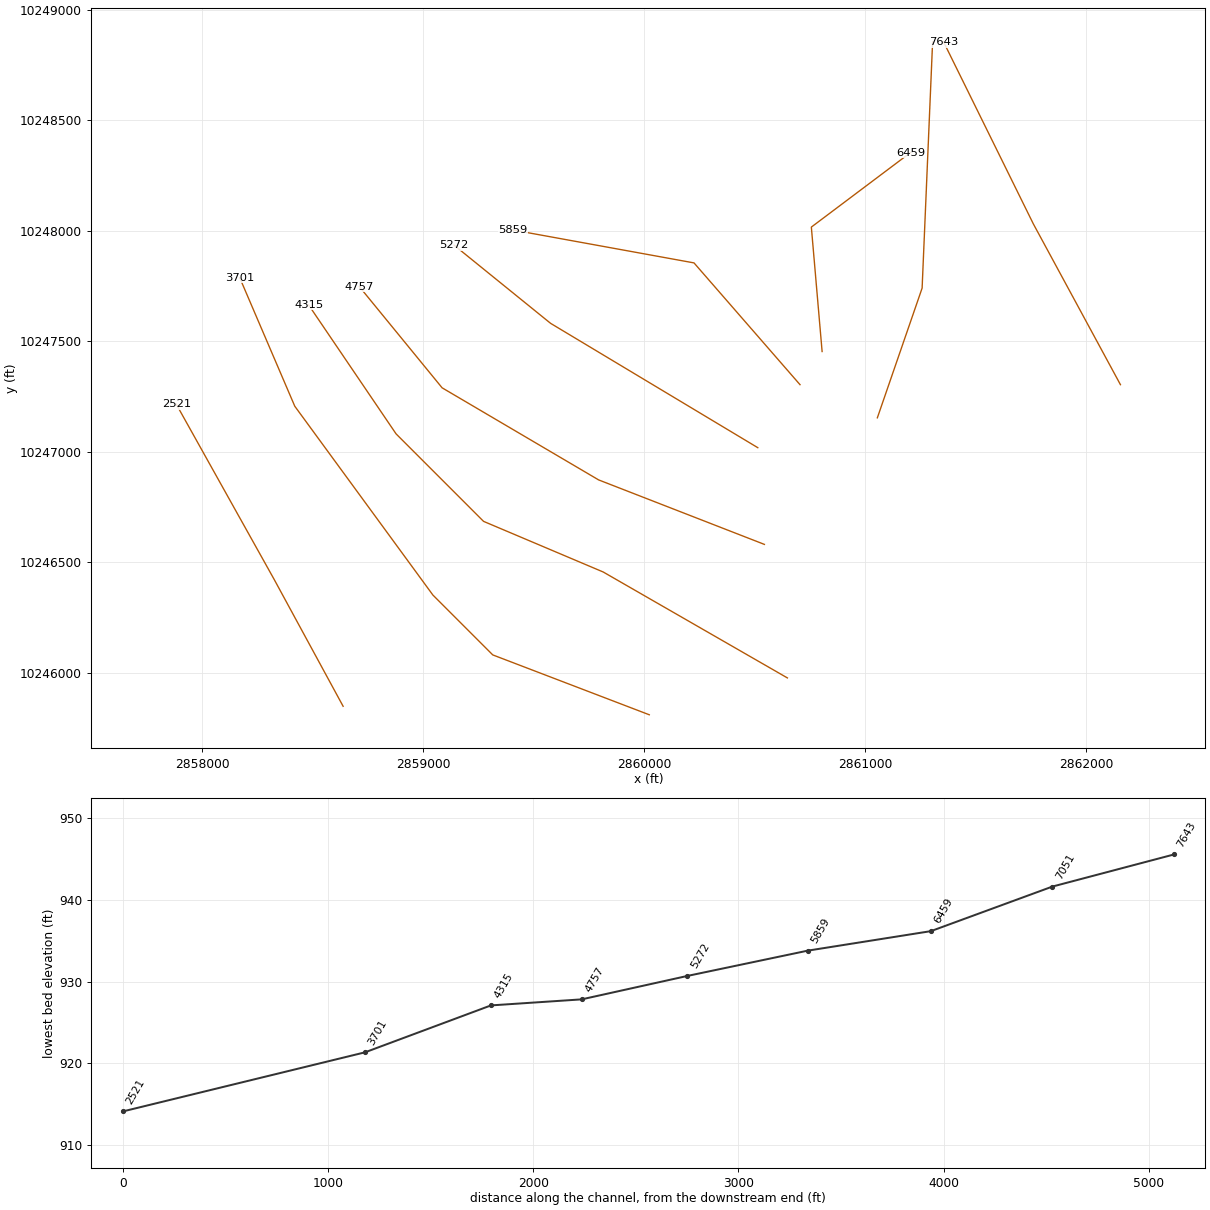
HEC-RAS study MILLER CREEK.prj: MILLER CREEK Base Level Engineering

--- MILLER CREEK.g01 (geometry) --- (continued)

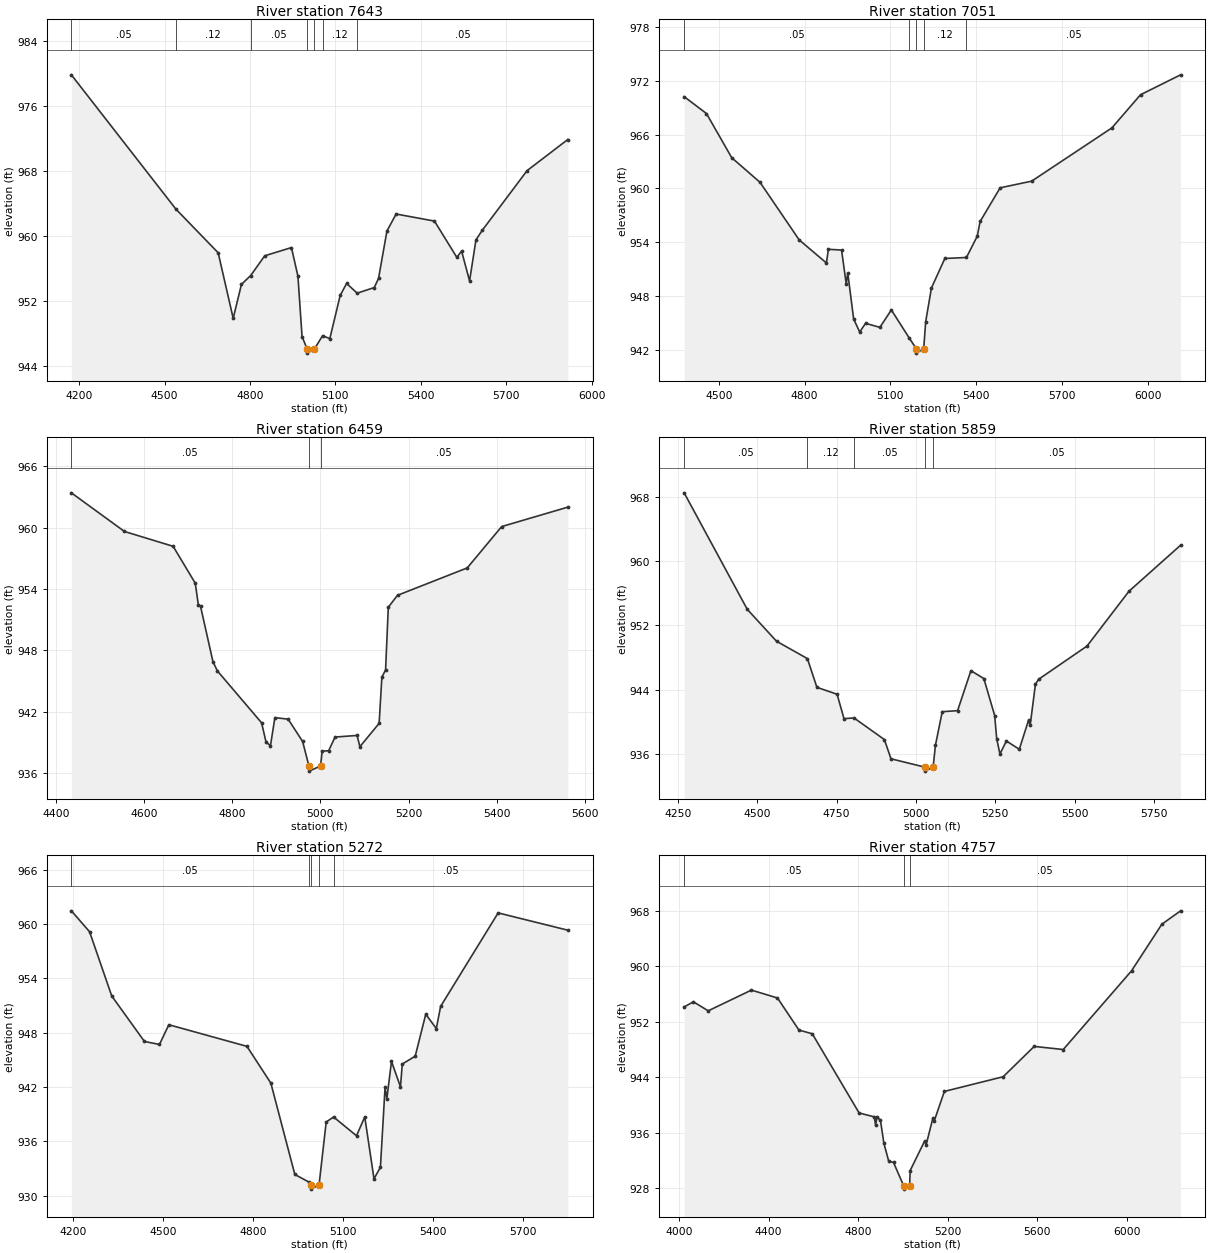
Type RM Length L Ch R = 1,7643,592,592,592
BEGIN DESCRIPTION:
MILLER CREEK 10.0
END DESCRIPTION:
XS GIS Cut Line= 3
      2862155.69     10247303.10      2861761.25     10248031.00
      2861355.69     10248853.11
#Sta/Elev= 30
  4172.1  979.84  4539.3  963.32  4688.0  957.94  4740.8  949.87  4769.8  954.05
  4802.3  955.14  4851.6  957.57  4945.5  958.58  4968.3  955.05  4982.8  947.63
  5000.7  946.09  5001.2  945.59  5026.3  946.09  5054.7  947.73  5080.4  947.38
  5116.9  952.70  5139.3  954.16  5176.6  952.97  5236.5  953.66  5251.6  954.79
  5281.1  960.62  5313.4  962.71  5448.1  961.84  5526.6  957.38  5543.5  958.14
  5571.5  954.47  5593.9  959.53  5616.4  960.72  5773.6  968.05  5916.7  971.88
#Mann=7,-1,0
  4172.1    0.05       0  4539.3    0.12       0  4802.3    0.05       0
  5000.7    0.05       0  5026.3    0.05       0  5054.7    0.12       0
  5176.6    0.05       0
Bank Sta=5000.7,5026.3
Exp/Cntr=0.3,0.1

Type RM Length L Ch R = 1,7051,592,592,592
BEGIN DESCRIPTION:
MILLER CREEK 9.0
END DESCRIPTION:
XS GIS Cut Line= 3
      2861055.67     10247153.08      2861258.25     10247740.00
      2861305.68     10248853.09
#Sta/Elev= 30
  4379.1  970.22  4457.1  968.34  4545.4  963.42  4644.3  960.68  4781.1  954.27
  4876.3  951.70  4883.2  953.22  4929.2  953.14  4945.6  949.37  4950.9  950.59
  4971.5  945.46  4992.7  944.01  5013.1  944.98  5063.2  944.53  5103.2  946.47
  5165.8  943.34  5190.2  942.16  5190.7  941.66  5216.3  942.16  5223.3  945.17
  5243.3  948.91  5290.2  952.20  5365.6  952.31  5403.5  954.68  5413.5  956.32
  5483.5  960.07  5593.6  960.81  5873.9  966.74  5974.0  970.43  6114.1  972.65
#Mann=5,-1,0
  4379.1    0.05       0  5165.8    0.12       0  5190.2    0.05       0
  5216.3    0.12       0  5365.6    0.05       0
Bank Sta=5190.2,5216.3
Exp/Cntr=0.3,0.1

Type RM Length L Ch R = 1,6459,600,600,600
BEGIN DESCRIPTION:
MILLER CREEK 8.0
END DESCRIPTION:
XS GIS Cut Line= 3
      2860805.69     10247453.10      2860757.00     10248016.00
      2861205.67     10248353.10
#Sta/Elev= 30
  4435.0  963.41  4555.5  959.63  4665.9  958.18  4716.1  954.57  4723.1  952.44
  4728.1  952.30  4756.2  946.90  4766.2  946.00  4866.6  940.92  4876.7  939.02
  4886.7  938.70  4896.7  941.43  4926.8  941.28  4959.6  939.10  4973.9  936.70
  4974.4  936.20  5000.2  936.70  5004.1  938.16  5018.6  938.19  5033.2  939.53
  5083.2  939.69  5089.5  938.59  5133.2  940.87  5139.4  945.39  5147.8  946.09
  5154.0  952.23  5174.9  953.39  5333.1  956.07  5411.1  960.11  5561.2  962.01
#Mann=3,-1,0
  4435.0    0.05       0  4973.9    0.05       0  5000.2    0.05       0
Bank Sta=4973.9,5000.2
Exp/Cntr=0.3,0.1

Type RM Length L Ch R = 1,5859,587,587,587
BEGIN DESCRIPTION:
MILLER CREEK 7.0
END DESCRIPTION:
XS GIS Cut Line= 3
      2860705.71     10247303.08      2860226.00     10247854.00
      2859405.64     10248003.12
#Sta/Elev= 30
  4269.5  968.56  4468.4  954.01  4560.6  950.03  4657.9  947.86  4687.8  944.27
  4751.4  943.41  4773.2  940.36  4804.8  940.45  4900.4  937.75  4921.3  935.35
  5027.8  934.31  5028.3  933.81  5054.1  934.31  5061.3  937.04  5082.8  941.23
  5131.1  941.36  5173.1  946.35  5213.8  945.37  5248.0  940.75  5254.4  937.84
  5264.6  935.95  5284.9  937.57  5325.6  936.54  5354.7  940.17  5359.8  939.53
  5376.4  944.66  5386.5  945.28  5539.0  949.43  5671.1  956.27  5833.8  962.02
#Mann=5,-1,0
  4269.5    0.05       0  4657.9    0.12       0  4804.8    0.05       0
  5027.8    0.05       0  5054.1    0.05       0
Bank Sta=5027.8,5054.1
Exp/Cntr=0.3,0.1

Type RM Length L Ch R = 1,5272,515,515,515
BEGIN DESCRIPTION:
Mapping XS b7a53bf5
END DESCRIPTION:
XS GIS Cut Line= 3
      2860514.65     10247018.04      2859577.11     10247580.56
      2859140.18     10247934.26
#Sta/Elev= 30
  4193.9  961.47  4254.6  959.16  4328.5  952.06  4437.6  947.03  4487.8  946.70
  4518.9  948.88  4779.4  946.49  4859.1  942.43  4939.1  932.33  4985.6  931.50
  4993.6  931.21  4994.1  930.71  5020.0  931.21  5043.7  938.13  5068.4  938.68
  5144.8  936.61  5172.3  938.69  5203.1  931.85  5224.5  933.13  5240.0  941.97
  5245.9  940.69  5261.4  944.82  5291.4  942.02  5297.4  944.54  5340.5  945.40
  5375.7  950.04  5410.9  948.46  5425.3  950.91  5617.1  961.24  5849.4  959.33
#Mann=5,-1,0
  4193.9    0.05       0  4985.6    0.12       0  4993.6    0.07       0
  5020.0    0.12       0  5068.4    0.05       0
Bank Sta=4993.6,5020
Exp/Cntr=0.3,0.1

Type RM Length L Ch R = 1,4757,442,442,442
BEGIN DESCRIPTION:
Mapping XS 5a540694
END DESCRIPTION:
XS GIS Cut Line= 4
      2860544.50     10246580.55      2859794.47     10246872.23
      2859086.14     10247288.89      2858711.16     10247747.20
#Sta/Elev= 30
  4022.6  954.11  4064.2  954.85  4130.1  953.55  4323.2  956.54  4439.8  955.40
  4535.5  950.78  4595.3  950.24  4804.6  938.82  4872.3  938.26  4878.3  937.06
  4884.1  938.20  4899.7  937.80  4915.4  934.44  4936.9  931.86  4958.3  931.69
  5003.3  928.34  5003.8  927.84  5030.5  928.34  5032.6  930.51  5097.0  934.75
  5104.4  934.26  5134.1  938.07  5139.9  937.64  5185.6  941.93  5448.5  944.05
  5587.1  948.42  5716.8  947.97  6021.9  959.31  6157.6  966.04  6241.3  967.97
#Mann=3,-1,0
  4022.6    0.05       0  5003.3    0.03       0  5030.5    0.05       0
Bank Sta=5003.3,5030.5
Exp/Cntr=0.3,0.1

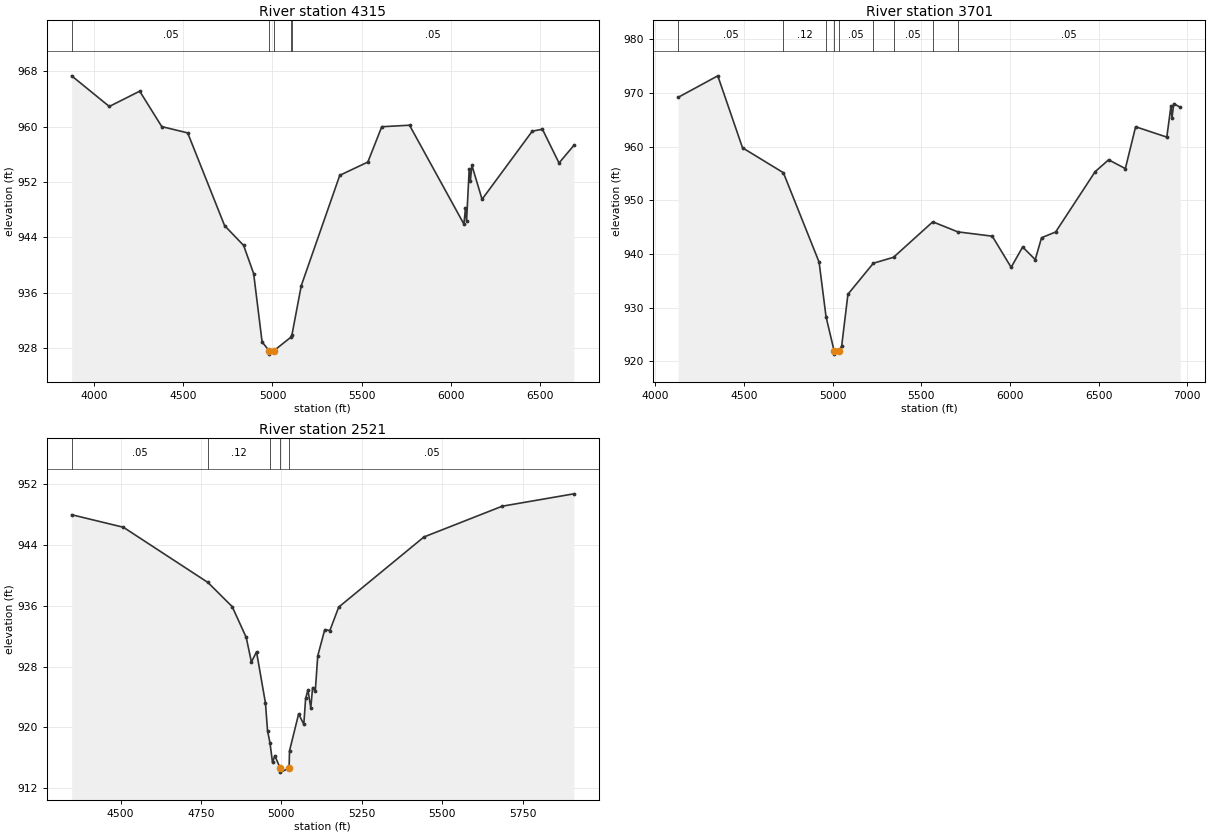
Type RM Length L Ch R = 1,4315,614,614,614
BEGIN DESCRIPTION:
Mapping XS cf6444f3
END DESCRIPTION:
XS GIS Cut Line= 5
      2860648.60     10245976.42      2859815.31     10246455.56
      2859273.64     10246684.73      2858877.81     10247080.56
      2858481.99     10247663.87
#Sta/Elev= 30
  3874.6  967.33  4085.6  962.90  4256.0  965.11  4379.6  959.99  4524.8  959.08
  4731.6  945.68  4838.3  942.81  4894.4  938.75  4941.8  928.86  4981.0  927.60
  4981.5  927.10  5008.2  927.60  5104.4  929.57  5108.7  929.83  5161.2  936.99
  5377.1  952.95  5534.5  954.87  5612.3  959.97  5767.9  960.19  6072.6  945.90
  6081.5  948.17  6087.5  946.34  6102.5  953.90  6108.5  952.07  6117.4  954.40
  6174.4  949.48  6455.8  959.33  6512.7  959.61  6605.6  954.73  6688.7  957.27
#Mann=5,-1,0
  3874.6    0.05       0  4981.0    0.05       0  5008.2    0.05       0
  5104.4    0.12       0  5108.7    0.05       0
Bank Sta=4981,5008.2
Exp/Cntr=0.3,0.1

Type RM Length L Ch R = 1,3701,1180,1180,1180
BEGIN DESCRIPTION:
Mapping XS aec17acb
END DESCRIPTION:
XS GIS Cut Line= 5
      2860023.61     10245809.74      2859315.31     10246080.56
      2859044.47     10246351.39      2858419.47     10247205.56
      2858170.26     10247787.07
#Sta/Elev= 30
  4128.4  969.15  4352.1  973.16  4491.7  959.76  4722.2  955.12  4923.6  938.47
  4962.7  928.31  5009.0  921.85  5009.5  921.35  5036.2  921.85  5050.9  922.85
  5086.2  932.50  5229.5  938.27  5343.4  939.38  5564.7  945.98  5706.0  944.11
  5900.2  943.31  6006.7  937.51  6071.6  941.30  6142.6  938.95  6178.1  943.02
  6257.7  944.09  6480.3  955.31  6556.5  957.53  6650.8  955.89  6708.8  963.68
  6884.7  961.75  6908.2  967.57  6913.7  965.29  6923.9  967.99  6960.8  967.29
#Mann=9,-1,0
  4128.4    0.05       0  4722.2    0.12       0  4962.7    0.05       0
  5009.0    0.05       0  5036.2    0.05       0  5229.5    0.12       0
  5343.4    0.05       0  5564.7    0.12       0  5706.0    0.05       0
Bank Sta=5009,5036.2
Exp/Cntr=0.3,0.1

Type RM Length L Ch R = 1,2521,0,0,0
BEGIN DESCRIPTION:
MILLER CREEK 1.0
END DESCRIPTION:
XS GIS Cut Line= 3
      2858638.24     10245848.10      2858326.75     10246421.00
      2857883.17     10247214.76
#Sta/Elev= 30
  4347.9  947.99  4508.8  946.34  4771.7  939.07  4847.0  935.90  4890.7  931.84
  4906.8  928.60  4922.7  929.94  4950.5  923.20  4956.9  919.57  4964.5  917.97
  4972.4  915.39  4979.6  916.27  4996.6  914.61  4997.1  914.11  5023.9  914.61
  5025.3  916.92  5053.7  921.78  5069.7  920.40  5075.4  923.81  5082.6  924.92
  5091.4  922.56  5097.1  925.24  5105.5  924.83  5113.1  929.42  5134.8  932.86
  5150.8  932.75  5178.2  935.83  5443.2  945.06  5686.5  949.11  5909.3  950.74
#Mann=5,-1,0
  4347.9    0.05       0  4771.7    0.12       0  4964.5    0.05       0
  4996.6    0.03       0  5023.9    0.05       0
Bank Sta=4996.6,5023.9
Exp/Cntr=0.3,0.1

Chan Stop Cuts=-1