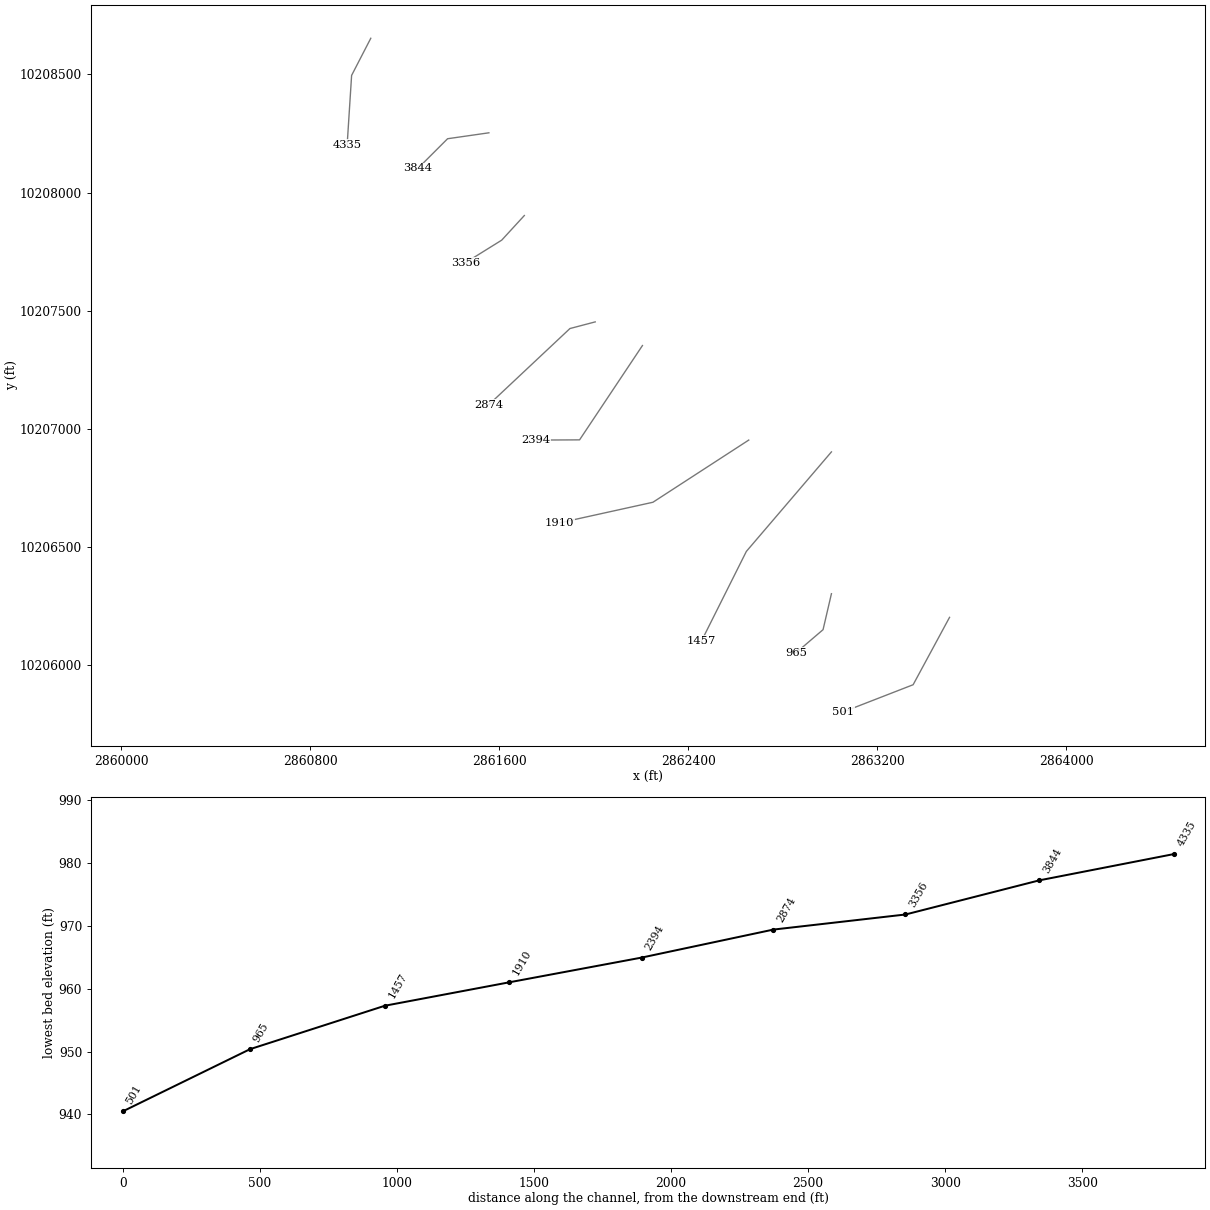
HEC-RAS study MOLASSES CREEK.prj: MOLASSES CREEK Base Level Engineering

--- MOLASSES CREEK.g01 (geometry) --- (continued)

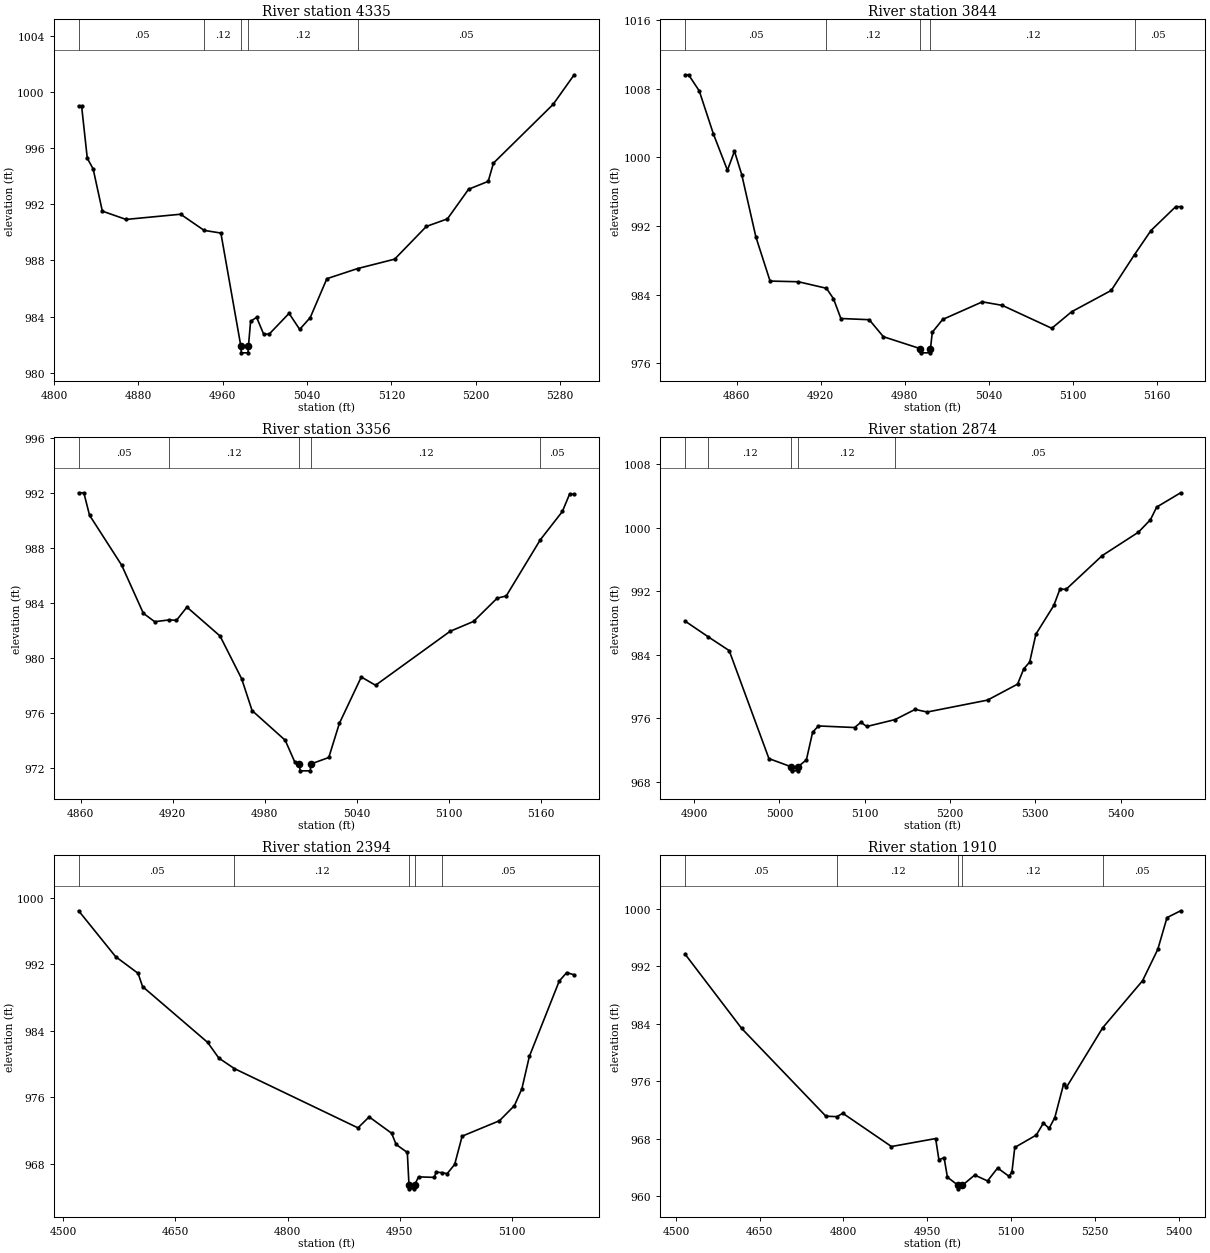
Type RM Length L Ch R = 1,4335,491,491,491
BEGIN DESCRIPTION:
MOLASSES CREEK 9.0
END DESCRIPTION:
XS GIS Cut Line= 3
      2861055.66     10208653.07      2860974.50     10208496.00
      2860955.68     10208203.10
#Sta/Elev= 30
  4823.2  999.01  4826.0  999.01  4831.4  995.28  4837.0  994.51  4845.7  991.51
  4868.2  990.92  4920.0  991.29  4942.3  990.14  4958.2  989.95  4977.1  981.92
  4977.6  981.42  4983.9  981.42  4984.4  981.92  4986.4  983.66  4992.1  983.95
  4998.8  982.75  5004.0  982.75  5022.9  984.23  5033.0  983.09  5043.0  983.93
  5058.8  986.70  5087.9  987.42  5123.1  988.09  5153.2  990.42  5173.2  990.96
  5193.3  993.07  5211.9  993.63  5216.9  994.93  5273.5  999.11  5293.5 1001.22
#Mann=5,-1,0
  4823.2    0.05       0  4942.3    0.12       0  4977.1    0.07       0
  4984.4    0.12       0  5087.9    0.05       0
Bank Sta=4977.1,4984.4
Exp/Cntr=0.3,0.1

Type RM Length L Ch R = 1,3844,488,488,488
BEGIN DESCRIPTION:
MOLASSES CREEK 8.0
END DESCRIPTION:
XS GIS Cut Line= 3
      2861555.66     10208253.11      2861380.75     10208228.00
      2861255.72     10208103.14
#Sta/Elev= 30
  4823.3 1009.63  4825.8 1009.63  4833.4 1007.75  4843.5 1002.73  4853.5  998.51
  4858.5 1000.73  4863.7  997.99  4873.8  990.73  4883.9  985.60  4904.1  985.52
  4924.1  984.76  4929.1  983.55  4934.4  981.24  4954.6  981.10  4964.7  979.12
  4990.8  977.74  4991.3  977.24  4997.8  977.24  4998.3  977.74  4999.6  979.64
  5007.0  981.13  5035.3  983.18  5049.5  982.77  5084.8  980.10  5099.0  982.03
  5127.2  984.51  5143.8  988.68  5155.5  991.48  5173.2  994.27  5176.7  994.27
#Mann=5,-1,0
  4823.3    0.05       0  4924.1    0.12       0  4990.8    0.07       0
  4998.3    0.12       0  5143.8    0.05       0
Bank Sta=4990.8,4998.3
Exp/Cntr=0.3,0.1

Type RM Length L Ch R = 1,3356,482,482,482
BEGIN DESCRIPTION:
MOLASSES CREEK 7.0
END DESCRIPTION:
XS GIS Cut Line= 3
      2861705.68     10207903.11      2861610.00     10207799.00
      2861455.67     10207703.10
#Sta/Elev= 30
  4858.6  992.02  4862.0  992.02  4865.7  990.39  4886.7  986.75  4900.8  983.26
  4908.2  982.65  4917.7  982.78  4922.4  982.75  4929.2  983.71  4950.8  981.61
  4964.9  978.50  4971.7  976.19  4993.3  974.03  4999.5  972.46  5002.5  972.31
  5003.0  971.81  5009.6  971.81  5010.1  972.31  5021.7  972.78  5028.6  975.26
  5042.9  978.63  5052.2  978.03  5100.8  981.95  5116.1  982.67  5131.5  984.36
  5137.4  984.52  5159.6  988.60  5174.0  990.66  5178.7  991.92  5181.7  991.92
#Mann=5,-1,0
  4858.6    0.05       0  4917.7    0.12       0  5002.5    0.07       0
  5010.1    0.12       0  5159.6    0.05       0
Bank Sta=5002.5,5010.1
Exp/Cntr=0.3,0.1

Type RM Length L Ch R = 1,2874,480,480,480
BEGIN DESCRIPTION:
MOLASSES CREEK 6.0
END DESCRIPTION:
XS GIS Cut Line= 3
      2862005.72     10207453.12      2861898.75     10207425.00
      2861555.71     10207103.13
#Sta/Elev= 30
  4889.4  988.25  4916.3  986.29  4941.1  984.54  4987.7  970.95  5014.0  969.91
  5014.5  969.41  5021.2  969.41  5021.7  969.91  5031.6  970.79  5038.9  974.26
  5045.7  975.06  5088.2  974.86  5095.5  975.52  5102.4  974.99  5135.6  975.86
  5159.1  977.14  5173.2  976.81  5244.0  978.31  5279.2  980.32  5286.5  982.25
  5293.4  983.10  5300.7  986.61  5321.7  990.22  5329.0  992.31  5335.9  992.23
  5378.4  996.49  5420.9  999.44  5435.0 1001.01  5442.3 1002.60  5470.4 1004.40
#Mann=5,-1,0
  4889.4    0.05       0  4916.3    0.12       0  5014.0    0.07       0
  5021.7    0.12       0  5135.6    0.05       0
Bank Sta=5014,5021.7
Exp/Cntr=0.3,0.1

Type RM Length L Ch R = 1,2394,484,484,484
BEGIN DESCRIPTION:
MOLASSES CREEK 5.0
END DESCRIPTION:
XS GIS Cut Line= 3
      2862205.67     10207353.08      2861939.50     10206954.00
      2861755.70     10206953.11
#Sta/Elev= 30
  4520.3  998.43  4569.8  992.91  4599.9  990.90  4605.9  989.31  4693.0  982.59
  4708.0  980.70  4728.9  979.43  4894.3  972.30  4909.3  973.62  4939.4  971.65
  4945.4  970.30  4960.4  969.34  4962.6  965.46  4963.1  964.96  4969.8  964.96
  4970.3  965.46  4975.4  966.40  4996.5  966.34  4998.9  966.96  5006.4  966.92
  5013.8  966.79  5023.8  967.90  5033.8  971.30  5083.8  973.16  5103.8  974.98
  5113.8  977.01  5123.8  980.90  5163.8  989.97  5173.8  990.99  5183.8  990.72
#Mann=5,-1,0
  4520.3    0.05       0  4728.9    0.12       0  4962.6    0.07       0
  4970.3    0.12       0  5006.4    0.05       0
Bank Sta=4962.6,4970.3
Exp/Cntr=0.3,0.1

Type RM Length L Ch R = 1,1910,453,453,453
BEGIN DESCRIPTION:
MOLASSES CREEK 4.0
END DESCRIPTION:
XS GIS Cut Line= 3
      2862655.65     10206953.09      2862250.00     10206690.00
      2861855.66     10206603.11
#Sta/Elev= 30
  4516.5  993.69  4617.7  983.36  4768.6  971.13  4788.3  971.07  4798.9  971.54
  4886.0  966.91  4965.1  968.02  4971.0  965.06  4980.2  965.37  4986.2  962.64
  5005.2  961.52  5005.7  961.02  5013.1  961.52  5035.1  962.94  5058.0  962.12
  5076.1  963.92  5096.6  962.76  5101.7  963.35  5106.8  966.78  5145.4  968.51
  5158.0  970.17  5168.3  969.44  5178.5  970.94  5194.3  975.61  5199.4  975.16
  5264.2  983.44  5335.6  989.99  5362.8  994.34  5379.4  998.78  5403.8  999.73
#Mann=5,-1,0
  4516.5    0.05       0  4788.3    0.12       0  5005.2    0.07       0
  5013.1    0.12       0  5264.2    0.05       0
Bank Sta=5005.2,5013.1
Exp/Cntr=0.3,0.1

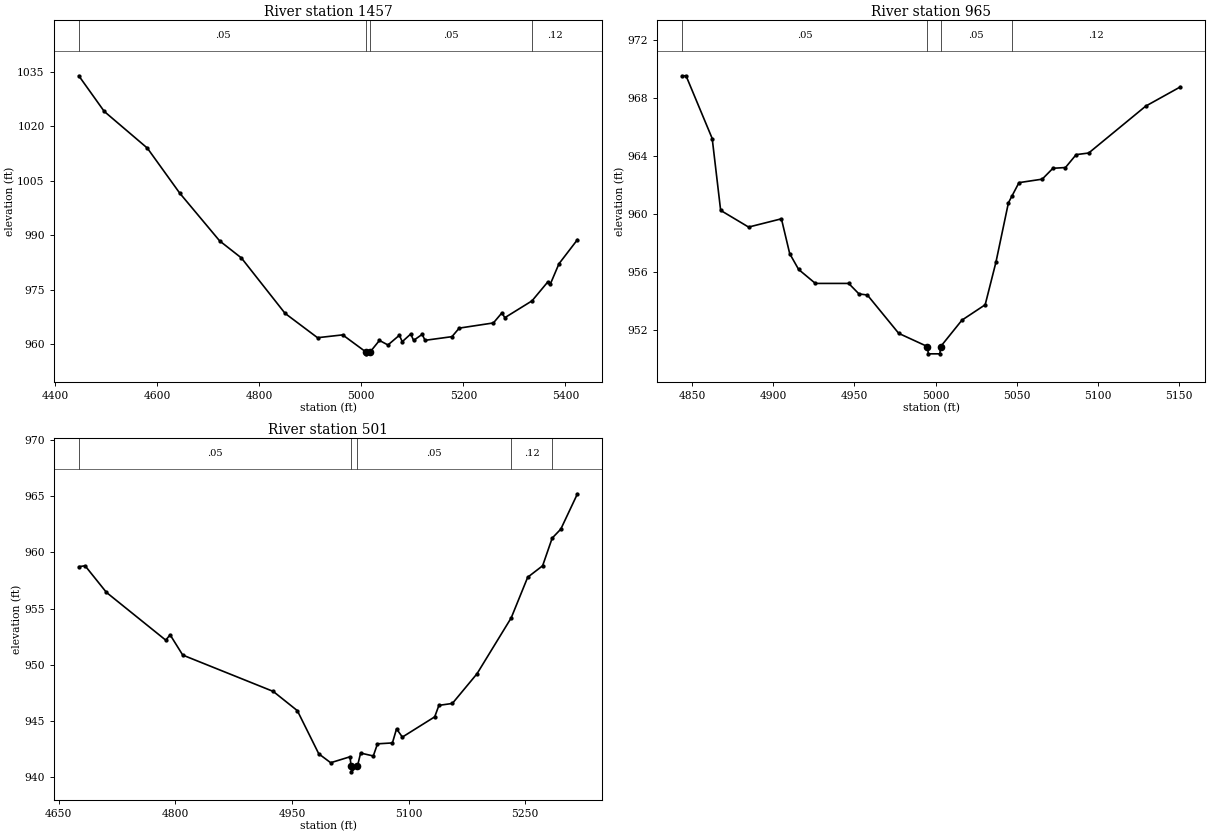
Type RM Length L Ch R = 1,1457,492,492,492
BEGIN DESCRIPTION:
MOLASSES CREEK 3.0
END DESCRIPTION:
XS GIS Cut Line= 3
      2863005.66     10206903.08      2862645.50     10206482.00
      2862455.67     10206103.09
#Sta/Elev= 30
  4445.9 1033.86  4495.8 1024.05  4580.3 1013.95  4644.0 1001.52  4722.2  988.39
  4764.8  983.70  4850.4  968.45  4914.1  961.74  4963.4  962.52  5009.1  957.80
  5009.6  957.30  5017.1  957.80  5035.5  960.99  5052.2  959.74  5074.6  962.42
  5080.2  960.64  5096.9  962.77  5102.5  960.99  5119.3  962.67  5124.9  961.02
  5177.7  962.03  5191.9  964.38  5259.0  965.81  5275.7  968.59  5281.3  967.25
  5334.7  971.89  5365.1  977.01  5370.7  976.53  5387.5  982.09  5423.8  988.74
#Mann=4,-1,0
  4445.9    0.05       0  5009.1    0.05       0  5017.1    0.05       0
  5334.7    0.12       0
Bank Sta=5009.1,5017.1
Exp/Cntr=0.3,0.1

Type RM Length L Ch R = 1,965,464,464,464
BEGIN DESCRIPTION:
MOLASSES CREEK 2.0
END DESCRIPTION:
XS GIS Cut Line= 3
      2863005.69     10206303.13      2862970.25     10206151.00
      2862855.68     10206053.11
#Sta/Elev= 30
  4843.8  969.54  4846.4  969.54  4862.5  965.22  4867.7  960.27  4884.9  959.12
  4905.1  959.69  4910.2  957.29  4915.7  956.20  4926.0  955.24  4946.5  955.24
  4952.8  954.52  4958.0  954.44  4977.3  951.80  4995.0  950.89  4995.5  950.39
  5002.6  950.39  5003.1  950.89  5016.2  952.71  5030.5  953.77  5037.1  956.69
  5044.8  960.79  5046.9  961.24  5051.3  962.18  5065.6  962.42  5072.2  963.17
  5079.9  963.22  5086.5  964.11  5094.2  964.22  5129.3  967.45  5150.7  968.78
#Mann=4,-1,0
  4843.8    0.05       0  4995.0    0.03       0  5003.1    0.05       0
  5046.9    0.12       0
Bank Sta=4995,5003.1
Exp/Cntr=0.3,0.1

Type RM Length L Ch R = 1,501,0,0,0
BEGIN DESCRIPTION:
MOLASSES CREEK 1.0
END DESCRIPTION:
XS GIS Cut Line= 3
      2863505.67     10206203.08      2863351.50     10205918.00
      2863055.72     10205803.13
#Sta/Elev= 30
  4675.9  958.74  4684.0  958.82  4711.5  956.45  4787.7  952.21  4793.4  952.68
  4809.6  950.88  4926.0  947.65  4957.0  945.94  4984.6  942.10  4999.9  941.31
  5024.8  941.84  5026.1  941.00  5026.6  940.50  5034.3  941.00  5038.4  942.17
  5054.7  941.91  5060.1  942.99  5079.3  943.07  5084.6  944.32  5092.1  943.59
  5133.7  945.39  5139.1  946.41  5156.4  946.58  5188.1  949.22  5232.1  954.19
  5253.3  957.80  5272.5  958.82  5284.8  961.28  5295.9  962.08  5317.3  965.22
#Mann=5,-1,0
  4675.9    0.05       0  5026.1    0.03       0  5034.3    0.05       0
  5232.1    0.12       0  5284.8    0.05       0
Bank Sta=5026.1,5034.3
Exp/Cntr=0.3,0.1

Chan Stop Cuts=-1