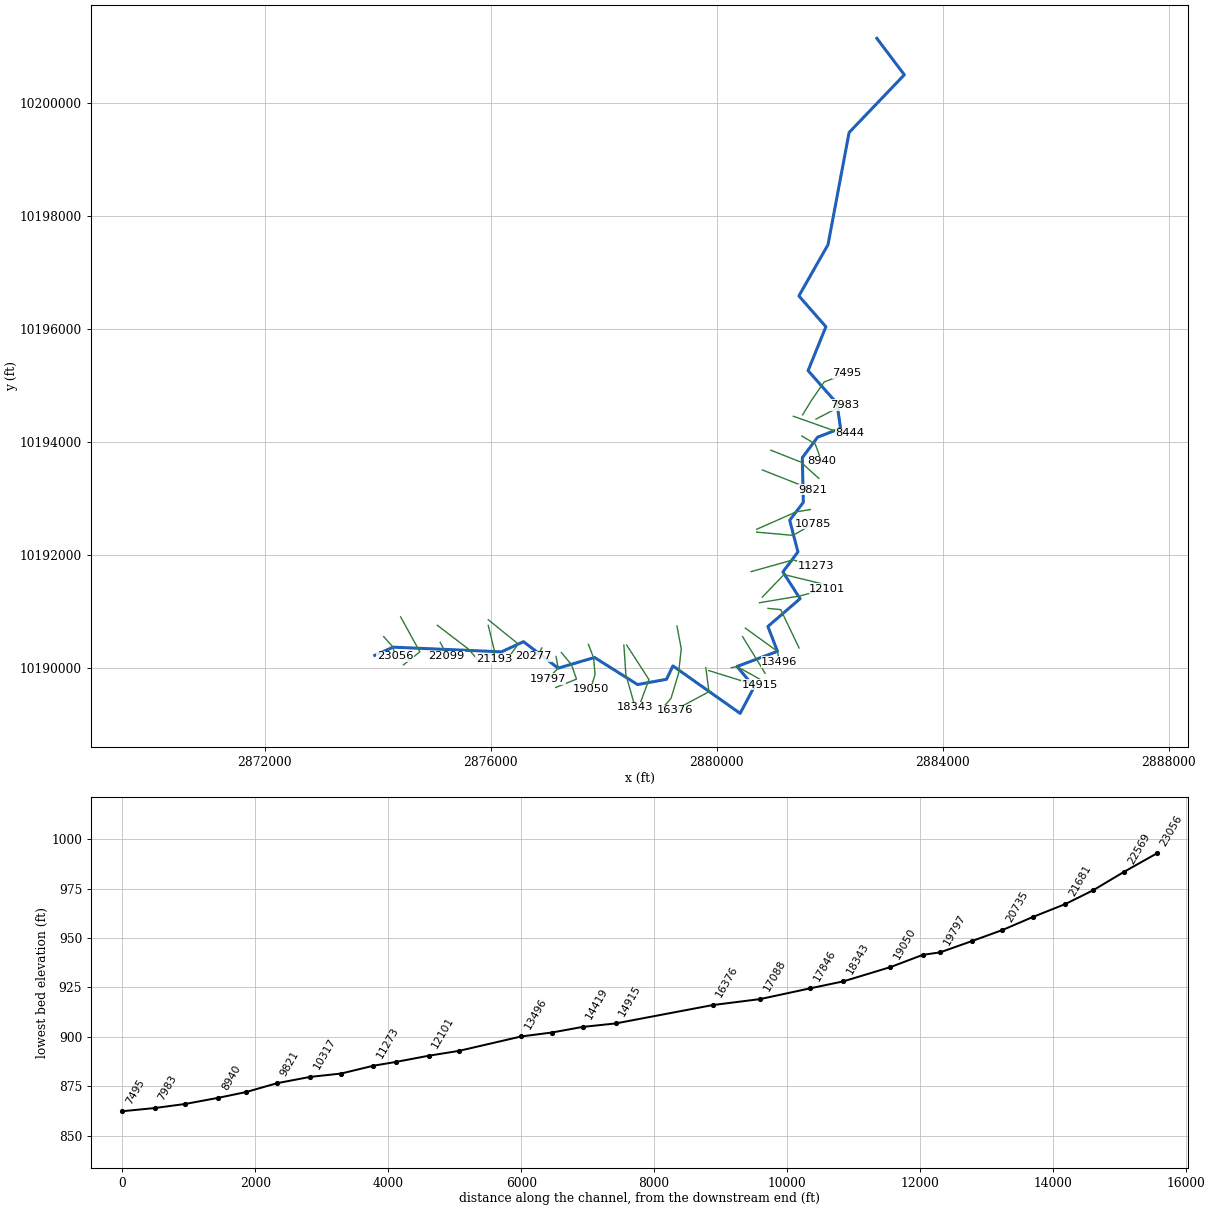
--- MOSS CREEK.prj (project) ---

Proj Title=MOSS CREEK Base Level Engineering
Current Plan=p01
Default Exp/Contr=0.3,0.1
English Units
Geom File=g01
Flow File=f01
Plan File=p01
BEGIN DESCRIPTION:
MOSS CREEK
END DESCRIPTION:

--- MOSS CREEK.p01 (plan) ---

Plan Title=Multiple Run
Short Identifier=Multiple
Geom File=g01
Flow File=f01
Subcritical Flow
K Sum by GR= 0
Std Step Tol= 0.01
Critical Tol= 0.01
Num of Std Step Trials= 20
Max Error Tol= 0.3
Flow Tol Ratio= 0.001
Split Flow NTrial= 30
Split Flow Tol= 0.02
Split Flow Ratio= 0.02
Log Output Level= 0
Friction Slope Method= 1
Unsteady Friction Slope Method= 2
Unsteady Bridges Friction Slope Method= 1
Parabolic Critical Depth
Global Vel Dist=  1 , 1 , 1
Global Log Level= 0
CheckData=True
Encroach Param= -1, 0, 0, 0
BEGIN DESCRIPTION:
Multiple Run
END DESCRIPTION:

--- MOSS CREEK.f01 (steady flow) ---

Flow Title=Multiple
Number of Profiles=7
Profile Names=10-year,25-year,50-year,1pct_min,100-year,1pct_plu,500-year
River Rch & RM= MOSS CREEK,Reach-1,23056
      69     128     198     102     309     932     808
River Rch & RM= MOSS CREEK,Reach-1,19050
     102     206     330     175     527    1592    1439
River Rch & RM= MOSS CREEK,Reach-1,12101
     139     291     473     254     767    2317    2148
River Rch & RM= MOSS CREEK,Reach-1,9358
     164     351     578     312     944    2849    2677
River Rch & RM= MOSS CREEK,Reach-1,4716
     193     419     694     377    1140    3443    3271
Boundary for River Rch & Prof#=MOSS CREEK,Reach-1,1
Up Type=0
Dn Type=3
Dn Slope=0.005
Boundary for River Rch & Prof#=MOSS CREEK,Reach-1,2
Up Type=0
Dn Type=3
Dn Slope=0.005
Boundary for River Rch & Prof#=MOSS CREEK,Reach-1,3
Up Type=0
Dn Type=3
Dn Slope=0.005
Boundary for River Rch & Prof#=MOSS CREEK,Reach-1,4
Up Type=0
Dn Type=3
Dn Slope=0.005
Boundary for River Rch & Prof#=MOSS CREEK,Reach-1,5
Up Type=0
Dn Type=3
Dn Slope=0.005
Boundary for River Rch & Prof#=MOSS CREEK,Reach-1,6
Up Type=0
Dn Type=3
Dn Slope=0.005
Boundary for River Rch & Prof#=MOSS CREEK,Reach-1,7
Up Type=0
Dn Type=3
Dn Slope=0.005

--- MOSS CREEK.g01 (geometry) ---

Geom Title=Existing Conditions

River Reach=MOSS CREEK,Reach-1
Reach XY= 30
      2873948.25     10190221.00      2874271.75     10190367.00
      2876191.50     10190284.00      2876579.50     10190464.00
      2877193.25     10189995.00      2877836.25     10190184.00
      2878597.75     10189705.00      2879109.25     10189798.00
      2879224.00     10190035.00      2880413.00     10189195.00
      2880661.75     10189665.00      2880357.00     10190025.00
      2881073.50     10190293.00      2880904.00     10190733.00
      2881473.75     10191225.00      2881169.50     10191698.00
      2881435.75     10192052.00      2881290.00     10192612.00
      2881530.75     10192930.00      2881513.25     10193720.00
      2881783.25     10194083.00      2882190.00     10194240.00
      2882125.25     10194682.00      2881615.25     10195261.00
      2881930.25     10196038.00      2881452.25     10196583.00
      2881967.75     10197490.00      2882340.75     10199475.00
      2883318.25     10200497.00      2882831.50     10201142.00

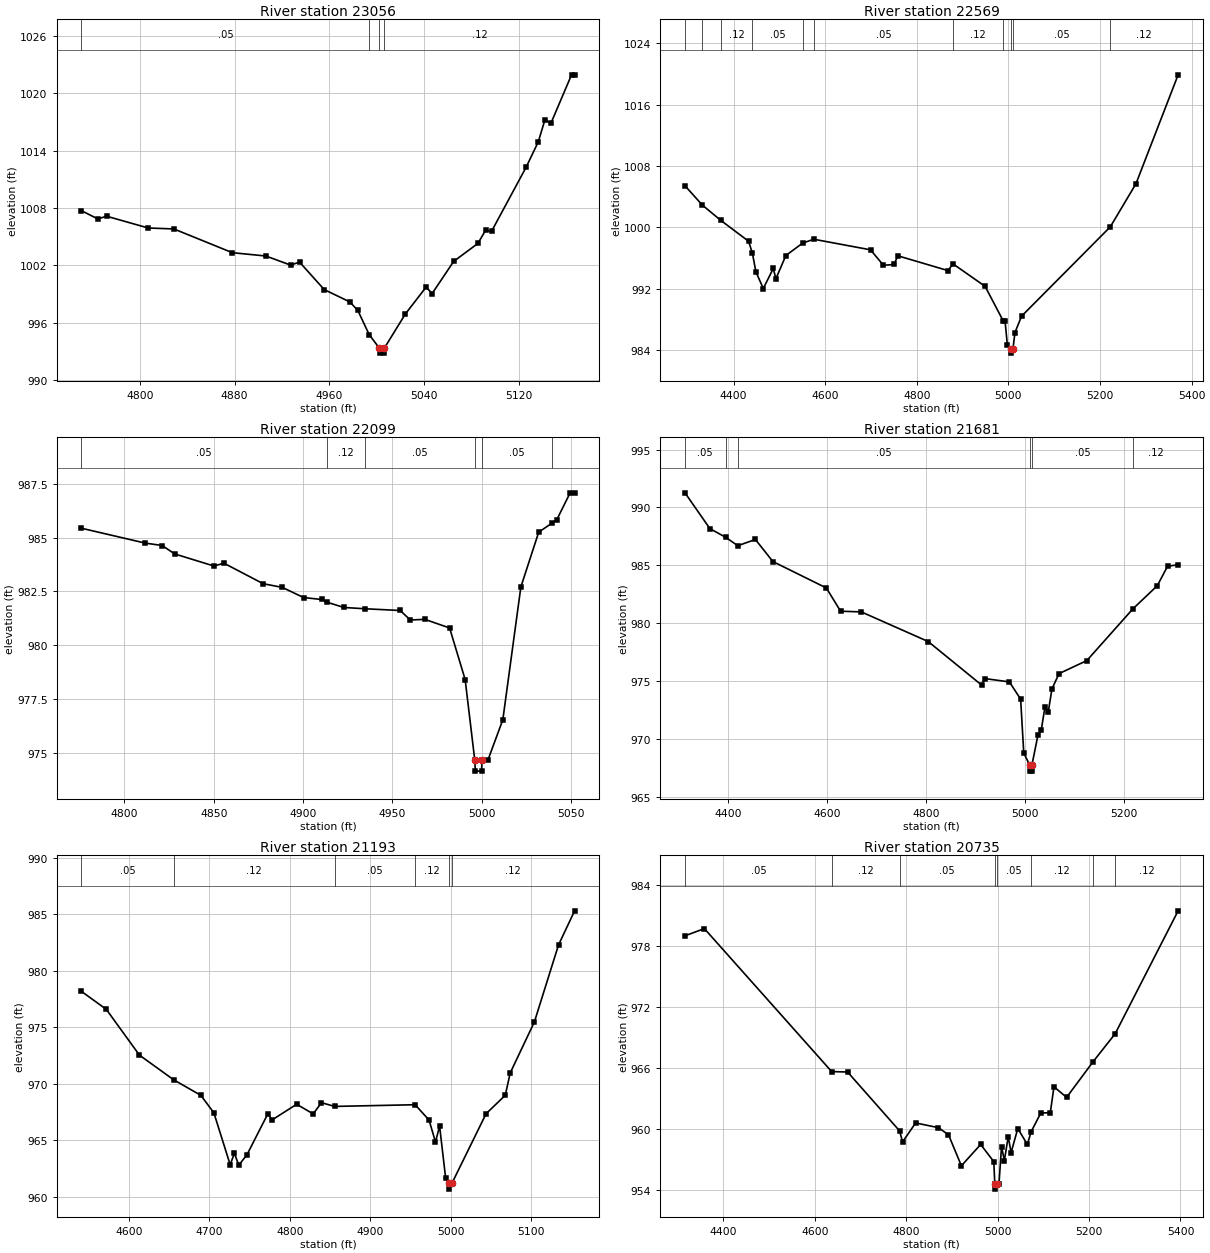
Type RM Length L Ch R = 1,23056,487,487,487
BEGIN DESCRIPTION:
MOSS CREEK 45.0
END DESCRIPTION:
XS GIS Cut Line= 3
      2874105.70     10190553.09      2874271.75     10190367.00
      2874305.69     10190203.08
#Sta/Elev= 30
  4750.6 1007.73  4764.4 1006.87  4771.9 1007.15  4807.0 1005.92  4828.7 1005.82
  4878.1 1003.34  4906.5 1002.99  4927.4 1002.04  4934.9 1002.36  4955.8  999.48
  4977.5  998.19  4984.2  997.30  4993.8  994.77  5002.5  993.34  5002.8  992.84
  5006.3  992.84  5006.5  993.34  5024.4  996.94  5041.9  999.74  5047.0  999.07
  5065.2 1002.43  5085.7 1004.31  5092.1 1005.67  5097.2 1005.57  5126.5 1012.29
  5136.7 1014.93  5142.3 1017.22  5147.4 1016.87  5164.8 1021.93  5167.4 1021.93
#Mann=4,-1,0
  4750.6    0.05       0  4993.8    0.12       0  5002.5    0.07       0
  5006.5    0.12       0
Bank Sta=5002.5,5006.5
Exp/Cntr=0.3,0.1

Type RM Length L Ch R = 1,22569,470,470,470
BEGIN DESCRIPTION:
MOSS CREEK 44.0
END DESCRIPTION:
XS GIS Cut Line= 3
      2874405.70     10190903.08      2874745.50     10190284.00
      2874455.72     10190053.14
#Sta/Elev= 30
  4293.8 1005.43  4331.5 1002.92  4371.7 1000.93  4432.6  998.20  4441.0  996.65
  4448.7  994.20  4464.8  992.04  4486.6  994.65  4492.3  993.31  4514.1  996.34
  4550.6  997.95  4574.9  998.46  4698.9  997.08  4727.2  995.06  4750.1  995.17
  4758.6  996.30  4867.6  994.38  4879.2  995.24  4949.1  992.32  4988.7  987.81
  4992.7  987.76  4997.7  984.66  5005.8  984.12  5006.1  983.62  5009.8  984.12
  5014.2  986.29  5028.6  988.43  5222.5 1000.08  5278.5 1005.70  5370.5 1019.88
#Mann=11,-1,0
  4293.8    0.12       0  4331.5    0.05       0  4371.7    0.12       0
  4441.0    0.05       0  4550.6    0.12       0  4574.9    0.05       0
  4879.2    0.12       0  4988.7    0.05       0  5005.8    0.05       0
  5009.8    0.05       0  5222.5    0.12       0
Bank Sta=5005.8,5009.8
Exp/Cntr=0.3,0.1

Type RM Length L Ch R = 1,22099,418,418,418
BEGIN DESCRIPTION:
MOSS CREEK 43.0
END DESCRIPTION:
XS GIS Cut Line= 3
      2875105.70     10190453.08      2875210.50     10190255.00
      2875205.69     10190203.12
#Sta/Elev= 30
  4775.9  985.43  4811.7  984.74  4821.1  984.63  4828.1  984.24  4850.1  983.68
  4855.7  983.81  4877.7  982.86  4888.4  982.69  4900.3  982.22  4910.4  982.13
  4913.2  982.01  4922.9  981.76  4934.8  981.70  4954.4  981.62  4960.1  981.18
  4968.2  981.21  4982.1  980.81  4990.8  978.42  4996.2  974.68  4996.5  974.18
  5000.0  974.18  5000.2  974.68  5003.5  974.68  5011.9  976.56  5022.0  982.71
  5032.0  985.25  5039.7  985.68  5042.1  985.82  5049.6  987.07  5052.1  987.07
#Mann=6,-1,0
  4775.9    0.05       0  4913.2    0.12       0  4934.8    0.05       0
  4996.2    0.05       0  5000.2    0.05       0  5039.7    0.12       0
Bank Sta=4996.2,5000.2
Exp/Cntr=0.3,0.1

Type RM Length L Ch R = 1,21681,488,488,488
BEGIN DESCRIPTION:
MOSS CREEK 42.0
END DESCRIPTION:
XS GIS Cut Line= 3
      2875055.72     10190753.08      2875602.00     10190336.00
      2875805.69     10190103.11
#Sta/Elev= 30
  4312.7  991.26  4363.0  988.17  4394.8  987.42  4419.5  986.69  4455.0  987.23
  4490.4  985.32  4598.4  983.04  4627.2  981.03  4669.1  980.97  4804.2  978.41
  4912.2  974.65  4918.5  975.21  4968.4  974.92  4991.1  973.43  4997.4  968.77
  5009.8  967.71  5010.1  967.21  5013.6  967.21  5013.8  967.71  5026.1  970.33
  5032.7  970.74  5040.3  972.78  5047.0  972.36  5054.5  974.33  5068.8  975.64
  5124.8  976.76  5217.9  981.23  5267.2  983.23  5288.0  984.91  5309.4  985.05
#Mann=6,-1,0
  4312.7    0.05       0  4394.8    0.12       0  4419.5    0.05       0
  5009.8    0.05       0  5013.8    0.05       0  5217.9    0.12       0
Bank Sta=5009.8,5013.8
Exp/Cntr=0.3,0.1

Type RM Length L Ch R = 1,21193,458,458,458
BEGIN DESCRIPTION:
MOSS CREEK 41.0
END DESCRIPTION:
XS GIS Cut Line= 3
      2875955.68     10190753.12      2876064.50     10190307.00
      2876055.69     10190153.15
#Sta/Elev= 30
  4540.8  978.16  4571.7  976.57  4612.9  972.52  4655.4  970.34  4689.3  968.96
  4705.5  967.41  4725.8  962.81  4731.0  963.85  4736.4  962.77  4746.7  963.71
  4772.7  967.34  4777.8  966.78  4808.4  968.17  4829.0  967.32  4839.3  968.31
  4855.7  967.98  4955.8  968.13  4973.1  966.77  4981.1  964.83  4986.2  966.24
  4993.7  961.65  4997.4  961.16  4997.7  960.66  5001.4  961.16  5044.0  967.33
  5067.9  968.97  5074.0  970.94  5104.1  975.46  5134.1  982.27  5154.1  985.29
#Mann=6,-1,0
  4540.8    0.05       0  4655.4    0.12       0  4855.7    0.05       0
  4955.8    0.12       0  4997.4    0.07       0  5001.4    0.12       0
Bank Sta=4997.4,5001.4
Exp/Cntr=0.3,0.1

Type RM Length L Ch R = 1,20735,458,458,458
BEGIN DESCRIPTION:
MOSS CREEK 40.0
END DESCRIPTION:
XS GIS Cut Line= 3
      2875955.67     10190853.12      2876487.25     10190423.00
      2876255.69     10190103.12
#Sta/Elev= 30
  4316.2  979.02  4358.6  979.73  4637.1  965.64  4671.9  965.60  4785.6  959.80
  4792.2  958.71  4820.7  960.58  4870.2  960.12  4892.6  959.42  4920.8  956.36
  4963.0  958.46  4991.7  956.77  4993.9  954.56  4994.2  954.06  4997.9  954.56
  5003.0  954.56  5008.6  958.25  5014.8  956.87  5023.3  959.24  5029.5  957.65
  5044.2  960.03  5065.1  958.46  5073.4  959.72  5094.5  961.56  5115.3  961.59
  5123.3  964.15  5150.9  963.10  5209.0  966.62  5257.3  969.38  5394.9  981.48
#Mann=8,-1,0
  4316.2    0.05       0  4637.1    0.12       0  4785.6    0.05       0
  4993.9    0.05       0  4997.9    0.05       0  5073.4    0.12       0
  5209.0    0.05       0  5257.3    0.12       0
Bank Sta=4993.9,4997.9
Exp/Cntr=0.3,0.1

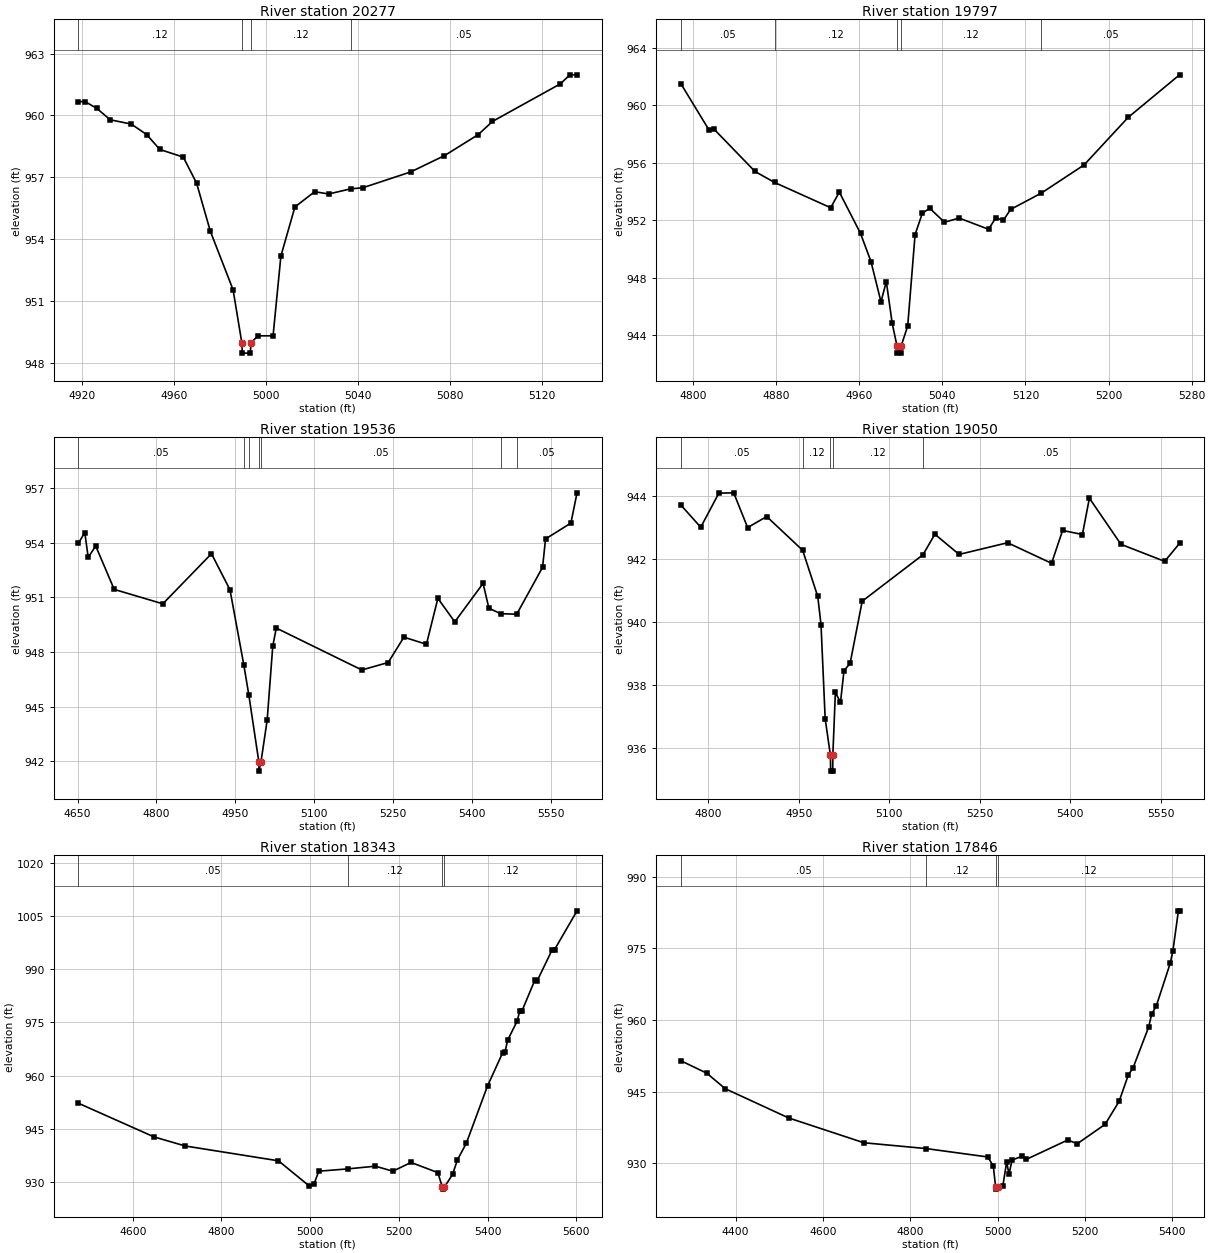
Type RM Length L Ch R = 1,20277,480,480,480
BEGIN DESCRIPTION:
MOSS CREEK 39.0
END DESCRIPTION:
XS GIS Cut Line= 3
      2876905.71     10190353.15      2876865.75     10190282.00
      2876755.70     10190203.12
#Sta/Elev= 30
  4918.4  960.67  4921.3  960.67  4926.4  960.34  4932.2  959.79  4941.4  959.58
  4948.1  959.07  4953.8  958.35  4964.0  957.98  4969.8  956.72  4975.8  954.38
  4985.7  951.54  4989.5  948.97  4989.7  948.47  4993.2  948.47  4993.5  948.97
  4996.5  949.31  5003.1  949.31  5006.5  953.18  5012.6  955.56  5021.2  956.30
  5027.3  956.19  5036.9  956.44  5042.1  956.49  5063.0  957.26  5077.7  958.05
  5092.4  959.07  5098.6  959.71  5128.1  961.53  5132.3  961.97  5135.4  961.97
#Mann=4,-1,0
  4918.4    0.12       0  4989.5    0.07       0  4993.5    0.12       0
  5036.9    0.05       0
Bank Sta=4989.5,4993.5
Exp/Cntr=0.3,0.1

Type RM Length L Ch R = 1,19797,261,261,261
BEGIN DESCRIPTION:
MOSS CREEK 38.0
END DESCRIPTION:
XS GIS Cut Line= 3
      2877155.68     10190203.14      2877193.25     10189995.00
      2877005.71     10189803.13
#Sta/Elev= 30
  4788.5  961.50  4815.3  958.31  4820.4  958.34  4859.7  955.40  4878.6  954.63
  4932.6  952.87  4940.9  953.96  4961.3  951.08  4971.4  949.11  4981.0  946.31
  4986.1  947.73  4991.8  944.81  4996.4  943.24  4996.7  942.74  5000.2  942.74
  5000.4  943.24  5006.7  944.63  5013.8  951.00  5020.8  952.49  5027.9  952.83
  5042.1  951.86  5056.2  952.15  5084.5  951.37  5091.5  952.17  5098.7  951.99
  5105.7  952.75  5135.3  953.89  5176.4  955.85  5218.8  959.16  5268.3  962.13
#Mann=5,-1,0
  4788.5    0.05       0  4878.6    0.12       0  4996.4    0.07       0
  5000.4    0.12       0  5135.3    0.05       0
Bank Sta=4996.4,5000.4
Exp/Cntr=0.3,0.1

Type RM Length L Ch R = 1,19536,486,486,486
BEGIN DESCRIPTION:
Mapping XS 7614348f
END DESCRIPTION:
XS GIS Cut Line= 4
      2877248.95     10190272.46      2877429.49     10190055.08
      2877517.93     10189800.83      2877150.03     10189653.67
#Sta/Elev= 30
  4651.7  953.98  4663.7  954.56  4670.2  953.20  4684.5  953.82  4719.7  951.44
  4812.1  950.65  4904.6  953.40  4939.8  951.42  4966.0  947.31  4975.5  945.67
  4994.7  941.97  4994.9  941.47  4998.7  941.97  5010.5  944.27  5021.1  948.32
  5027.8  949.32  5190.5  947.02  5240.6  947.43  5270.5  948.82  5313.3  948.43
  5335.1  950.95  5367.2  949.66  5421.0  951.77  5432.1  950.41  5454.2  950.11
  5485.0  950.08  5534.1  952.65  5539.8  954.21  5588.0  955.08  5599.7  956.74
#Mann=7,-1,0
  4651.7    0.05       0  4966.0    0.12       0  4975.5    0.05       0
  4994.7    0.05       0  4998.7    0.05       0  5454.2    0.12       0
  5485.0    0.05       0
Bank Sta=4994.7,4998.7
Exp/Cntr=0.3,0.1

Type RM Length L Ch R = 1,19050,707,707,707
BEGIN DESCRIPTION:
Mapping XS 0d2e7cb5
END DESCRIPTION:
XS GIS Cut Line= 4
      2877727.95     10190416.20      2877820.08     10190176.67
      2877845.87     10189885.58      2877764.80     10189620.26
#Sta/Elev= 30
  4754.8  943.70  4787.6  943.00  4817.6  944.08  4842.2  944.09  4865.3  942.99
  4896.9  943.34  4956.5  942.27  4981.5  940.81  4986.9  939.92  4993.8  936.94
  5002.5  935.78  5002.8  935.28  5006.3  935.28  5006.5  935.78  5010.7  937.77
  5019.2  937.46  5025.0  938.46  5035.1  938.69  5055.2  940.66  5155.9  942.13
  5175.6  942.78  5215.8  942.14  5296.1  942.51  5369.0  941.86  5387.3  942.90
  5420.1  942.77  5431.7  943.92  5484.0  942.46  5556.5  941.92  5581.1  942.49
#Mann=5,-1,0
  4754.8    0.05       0  4956.5    0.12       0  5002.5    0.07       0
  5006.5    0.12       0  5155.9    0.05       0
Bank Sta=5002.5,5006.5
Exp/Cntr=0.3,0.1

Type RM Length L Ch R = 1,18343,497,497,497
BEGIN DESCRIPTION:
MOSS CREEK 35.0
END DESCRIPTION:
XS GIS Cut Line= 3
      2878355.68     10190403.10      2878391.00     10189882.00
      2878555.70     10189303.07
#Sta/Elev= 30
  4477.7  952.24  4648.1  942.77  4718.2  940.22  4928.7  936.04  4997.7  928.99
  5009.2  929.65  5019.6  933.12  5084.4  933.76  5147.3  934.53  5186.4  933.11
  5227.6  935.58  5288.0  932.72  5298.3  928.57  5298.6  928.07  5302.4  928.57
  5321.1  932.19  5332.3  936.33  5352.3  941.01  5400.0  957.10  5433.9  966.39
  5439.1  966.60  5445.9  970.13  5466.7  975.33  5472.9  978.31  5478.1  978.35
  5506.8  986.91  5512.0  986.70  5545.9  995.47  5551.1  995.48  5601.9 1006.41
#Mann=4,-1,0
  4477.7    0.05       0  5084.4    0.12       0  5298.3    0.05       0
  5302.4    0.12       0
Bank Sta=5298.3,5302.4
Exp/Cntr=0.3,0.1

Type RM Length L Ch R = 1,17846,758,758,758
BEGIN DESCRIPTION:
MOSS CREEK 34.0
END DESCRIPTION:
XS GIS Cut Line= 3
      2878405.66     10190403.14      2878799.00     10189794.00
      2878655.70     10189403.14
#Sta/Elev= 30
  4274.9  951.45  4334.0  948.85  4376.2  945.60  4521.4  939.47  4693.6  934.27
  4836.2  933.05  4977.3  931.29  4989.9  929.40  4995.2  925.05  4995.5  924.55
  5000.0  925.05  5011.6  925.12  5020.5  930.21  5025.9  927.71  5032.9  930.64
  5056.4  931.46  5064.9  930.76  5160.7  934.86  5182.0  934.05  5245.9  938.13
  5277.9  942.93  5299.2  948.52  5309.6  949.90  5345.4  958.47  5352.4  961.19
  5363.1  962.95  5395.0  971.90  5401.1  974.49  5413.7  982.88  5416.3  982.88
#Mann=4,-1,0
  4274.9    0.05       0  4836.2    0.12       0  4995.2    0.07       0
  5000.0    0.12       0
Bank Sta=4995.2,5000
Exp/Cntr=0.3,0.1

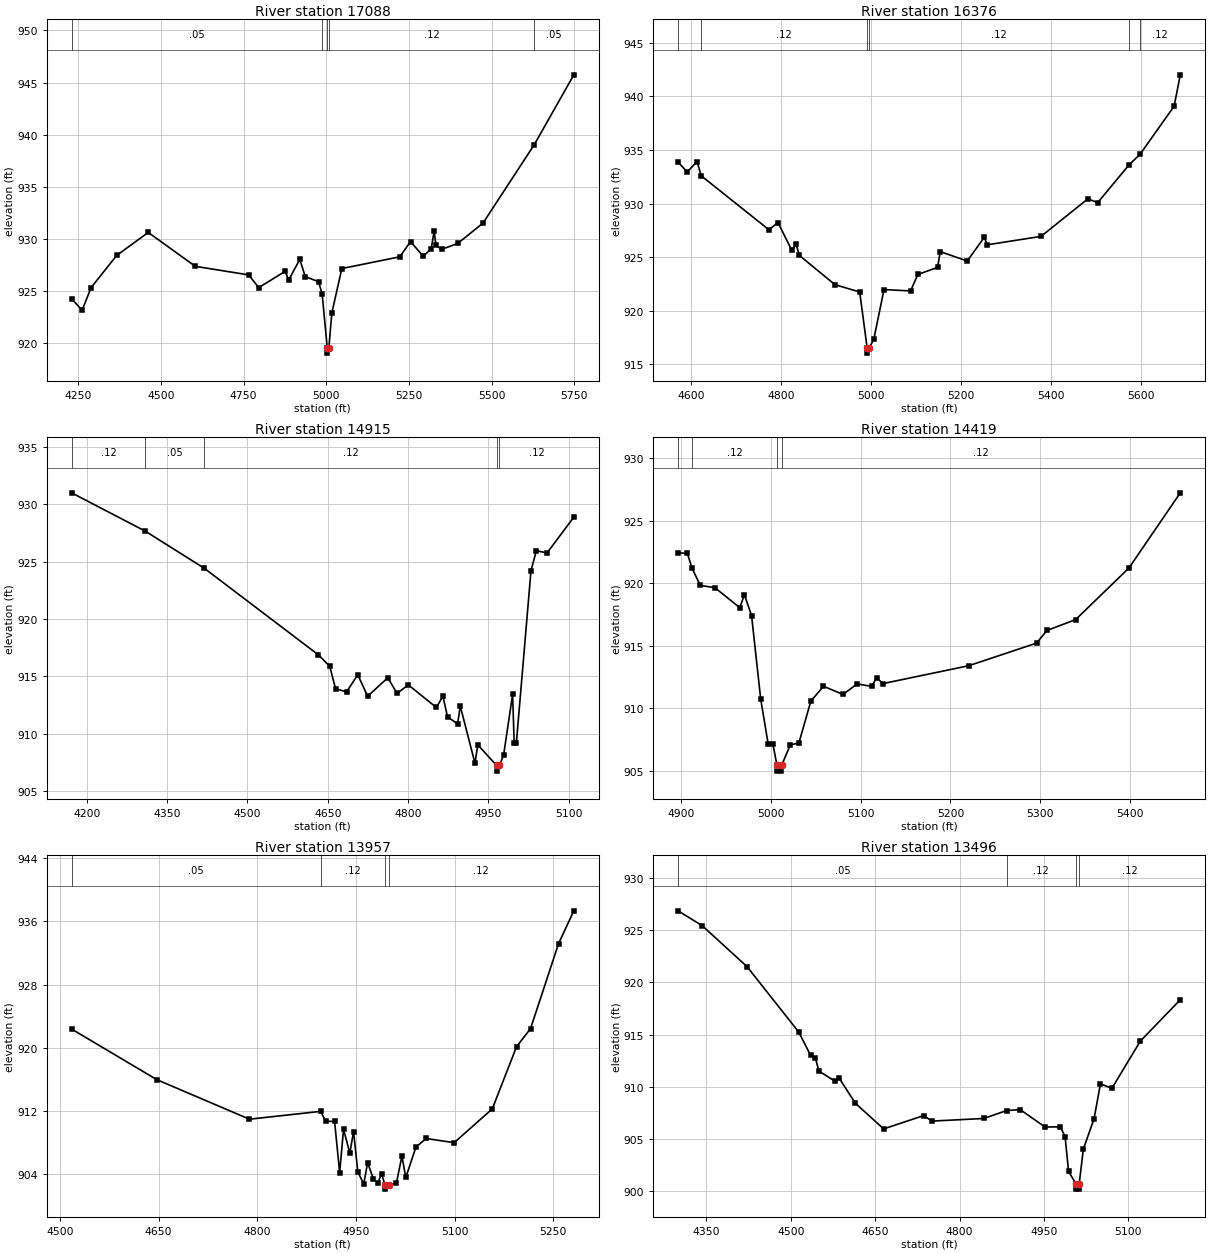
Type RM Length L Ch R = 1,17088,712,712,712
BEGIN DESCRIPTION:
Mapping XS 4b47ad8d
END DESCRIPTION:
XS GIS Cut Line= 5
      2879295.04     10190740.67      2879371.42     10190337.91
      2879322.81     10189900.41      2879190.87     10189462.91
      2879051.95     10189303.15
#Sta/Elev= 30
  4230.2  924.28  4261.9  923.18  4288.8  925.34  4366.5  928.44  4461.8  930.64
  4604.3  927.39  4765.7  926.57  4795.9  925.35  4876.4  926.92  4886.4  926.07
  4920.1  928.05  4936.8  926.40  4977.0  925.92  4987.9  924.72  5003.2  919.57
  5003.6  919.07  5008.0  919.57  5017.2  922.94  5047.4  927.18  5222.4  928.30
  5255.1  929.76  5293.6  928.36  5317.7  929.09  5326.6  930.77  5331.8  929.41
  5349.1  929.02  5397.7  929.58  5474.4  931.54  5629.4  939.06  5749.0  945.75
#Mann=5,-1,0
  4230.2    0.05       0  4987.9    0.12       0  5003.2    0.07       0
  5008.0    0.12       0  5629.4    0.05       0
Bank Sta=5003.2,5008
Exp/Cntr=0.3,0.1

Type RM Length L Ch R = 1,16376,1461,1461,1461
BEGIN DESCRIPTION:
MOSS CREEK 32.0
END DESCRIPTION:
XS GIS Cut Line= 3
      2879805.68     10190003.12      2879861.00     10189578.00
      2879255.68     10189253.11
#Sta/Elev= 30
  4571.3  933.86  4591.5  932.95  4613.4  933.92  4622.4  932.60  4773.0  927.56
  4793.2  928.23  4823.4  925.67  4833.5  926.20  4840.5  925.17  4919.6  922.44
  4974.7  921.75  4991.2  916.55  4991.6  916.05  4996.1  916.55  5006.0  917.34
  5028.7  921.98  5087.7  921.85  5104.0  923.39  5147.8  924.05  5153.6  925.52
  5213.6  924.64  5251.8  926.87  5257.5  926.15  5377.6  926.94  5481.6  930.44
  5503.5  930.09  5572.9  933.60  5597.6  934.60  5673.2  939.08  5687.0  942.01
#Mann=6,-1,0
  4571.3    0.05       0  4622.4    0.12       0  4991.2    0.07       0
  4996.1    0.12       0  5572.9    0.05       0  5597.6    0.12       0
Bank Sta=4991.2,4996.1
Exp/Cntr=0.3,0.1

Type RM Length L Ch R = 1,14915,496,496,496
BEGIN DESCRIPTION:
MOSS CREEK 31.0
END DESCRIPTION:
XS GIS Cut Line= 3
      2879855.67     10189953.11      2880646.25     10189707.00
      2880755.68     10189703.11
#Sta/Elev= 30
  4172.0  931.00  4309.4  927.66  4419.7  924.42  4632.8  916.87  4653.8  915.88
  4664.7  913.92  4685.2  913.65  4706.2  915.14  4724.5  913.27  4762.3  914.88
  4779.5  913.51  4800.4  914.26  4852.8  912.29  4865.1  913.27  4873.7  911.46
  4892.4  910.87  4897.6  912.39  4924.9  907.43  4930.2  909.03  4965.2  907.24
  4965.7  906.74  4970.7  907.24  4978.5  908.18  4995.2  913.42  4998.1  909.20
  5002.2  909.20  5029.5  924.21  5039.5  925.95  5059.5  925.76  5109.5  928.88
#Mann=5,-1,0
  4172.0    0.12       0  4309.4    0.05       0  4419.7    0.12       0
  4965.2    0.07       0  4970.7    0.12       0
Bank Sta=4965.2,4970.7
Exp/Cntr=0.3,0.1

Type RM Length L Ch R = 1,14419,462,462,462
BEGIN DESCRIPTION:
MOSS CREEK 30.0
END DESCRIPTION:
XS GIS Cut Line= 3
      2880255.64     10190003.10      2880357.00     10190025.00
      2880755.71     10189803.10
#Sta/Elev= 30
  4896.3  922.43  4906.6  922.38  4911.9  921.19  4921.0  919.82  4937.3  919.64
  4965.1  918.04  4970.2  919.08  4978.2  917.41  4988.4  910.73  4996.8  907.12
  5002.1  907.12  5006.4  905.48  5006.8  904.98  5011.5  904.98  5012.0  905.48
  5021.4  907.09  5030.9  907.21  5044.3  910.57  5058.4  911.76  5080.1  911.11
  5096.1  911.95  5112.1  911.75  5117.8  912.46  5124.4  911.97  5220.7  913.41
  5296.0  915.21  5307.6  916.22  5339.6  917.09  5399.0  921.21  5456.3  927.22
#Mann=4,-1,0
  4896.3    0.05       0  4911.9    0.12       0  5006.4    0.07       0
  5012.0    0.12       0
Bank Sta=5006.4,5012
Exp/Cntr=0.3,0.1

Type RM Length L Ch R = 1,13957,461,461,461
BEGIN DESCRIPTION:
MOSS CREEK 29.0
END DESCRIPTION:
XS GIS Cut Line= 3
      2880455.70     10190553.08      2880709.00     10190143.00
      2880855.69     10189903.10
#Sta/Elev= 30
  4518.0  922.38  4647.4  915.99  4788.2  910.99  4896.4  911.98  4904.0  910.74
  4917.6  910.70  4925.3  904.24  4931.2  909.71  4940.7  906.71  4946.5  909.41
  4952.9  904.33  4961.9  902.80  4967.8  905.50  4976.4  903.47  4983.2  902.92
  4989.1  904.10  4994.2  902.65  4994.6  902.15  4999.8  902.65  5011.6  902.93
  5019.9  906.32  5025.8  903.62  5041.2  907.46  5056.7  908.55  5099.3  908.02
  5157.3  912.30  5194.1  920.15  5215.4  922.44  5258.0  933.19  5281.2  937.33
#Mann=4,-1,0
  4518.0    0.05       0  4896.4    0.12       0  4994.2    0.07       0
  4999.8    0.12       0
Bank Sta=4994.2,4999.8
Exp/Cntr=0.3,0.1

Type RM Length L Ch R = 1,13496,938,938,938
BEGIN DESCRIPTION:
MOSS CREEK 28.0
END DESCRIPTION:
XS GIS Cut Line= 3
      2880505.71     10190703.09      2881073.50     10190293.00
      2881105.68     10190103.11
#Sta/Elev= 30
  4299.6  926.87  4342.5  925.44  4422.2  921.51  4514.2  915.23  4535.1  913.01
  4543.7  912.77  4549.8  911.49  4579.2  910.50  4585.4  910.86  4614.8  908.40
  4665.1  905.94  4736.3  907.22  4751.0  906.69  4843.0  906.94  4883.7  907.70
  4908.0  907.79  4952.1  906.12  4979.2  906.14  4987.7  905.21  4993.9  901.86
  5007.2  900.66  5007.7  900.16  5012.4  900.16  5012.8  900.66  5020.2  904.01
  5039.2  906.91  5050.6  910.27  5070.9  909.83  5121.6  914.37  5192.6  918.34
#Mann=4,-1,0
  4299.6    0.05       0  4883.7    0.12       0  5007.2    0.07       0
  5012.8    0.12       0
Bank Sta=5007.2,5012.8
Exp/Cntr=0.3,0.1

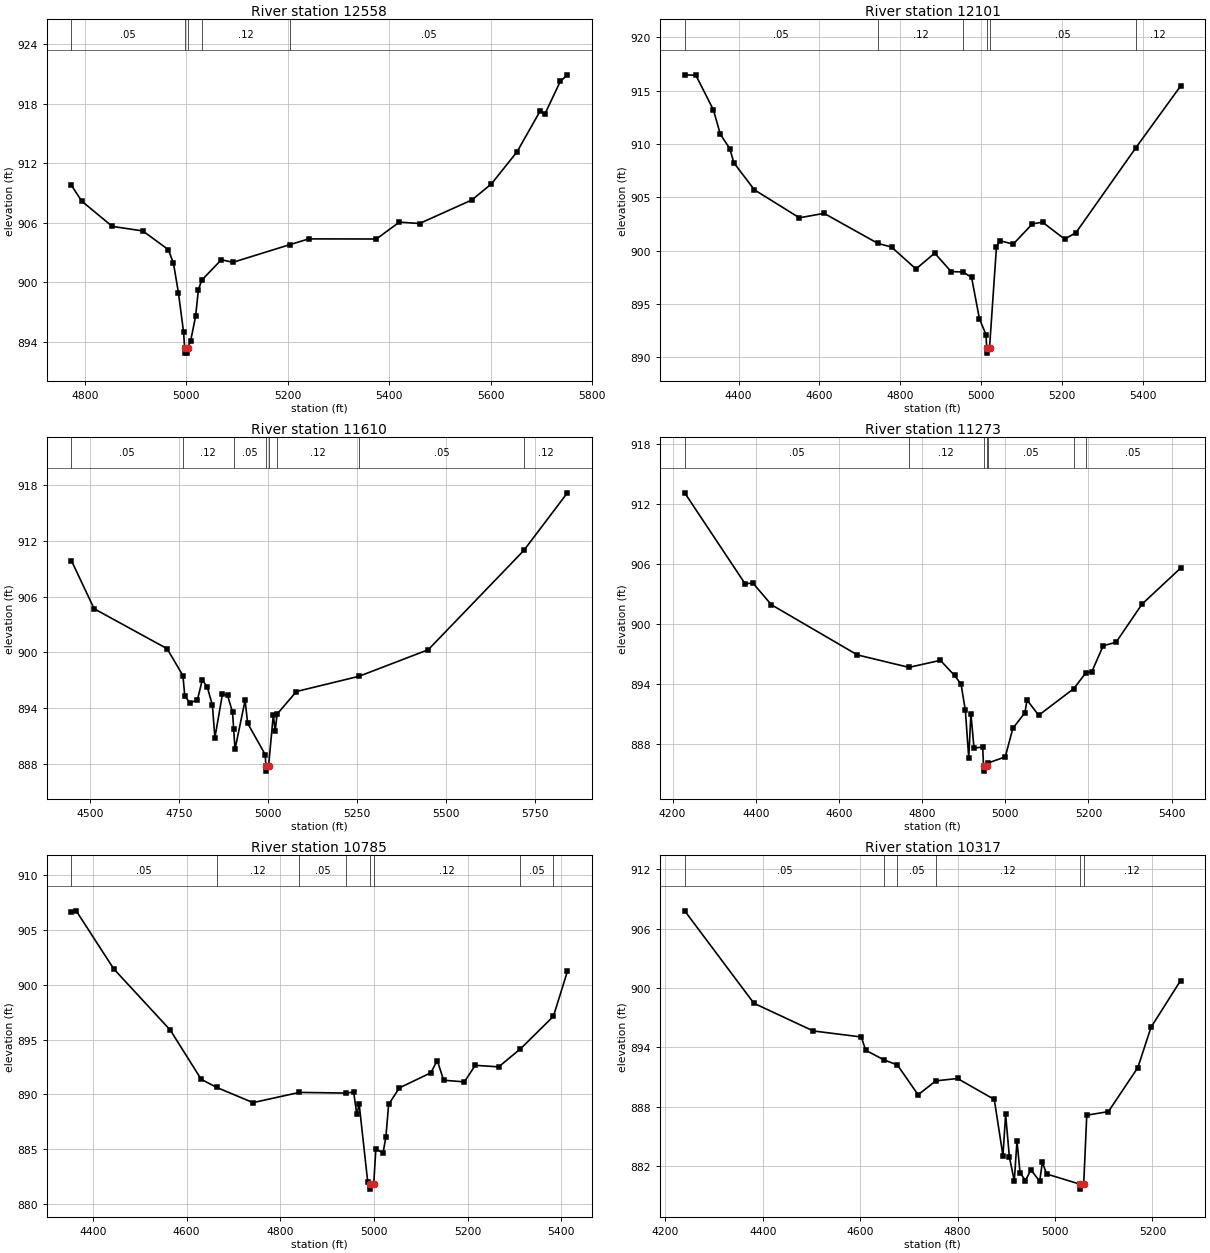
Type RM Length L Ch R = 1,12558,457,457,457
BEGIN DESCRIPTION:
MOSS CREEK 27.0
END DESCRIPTION:
XS GIS Cut Line= 3
      2880905.68     10191053.11      2881131.00     10191031.00
      2881455.67     10190353.14
#Sta/Elev= 30
  4773.6  909.75  4793.7  908.17  4854.0  905.62  4914.3  905.16  4964.5  903.28
  4974.6  901.95  4984.6  898.91  4994.7  894.96  4996.8  893.35  4997.3  892.85
  5002.1  892.85  5002.5  893.35  5008.7  894.10  5018.4  896.56  5023.9  899.23
  5030.3  900.19  5069.2  902.26  5091.9  902.00  5203.6  903.77  5241.6  904.36
  5374.9  904.35  5420.3  906.05  5460.0  905.91  5563.1  908.28  5601.6  909.89
  5652.4  913.14  5697.7  917.23  5707.3  916.95  5737.5  920.22  5751.6  920.89
#Mann=5,-1,0
  4773.6    0.05       0  4996.8    0.05       0  5002.5    0.05       0
  5030.3    0.12       0  5203.6    0.05       0
Bank Sta=4996.8,5002.5
Exp/Cntr=0.3,0.1

Type RM Length L Ch R = 1,12101,491,491,491
BEGIN DESCRIPTION:
MOSS CREEK 26.0
END DESCRIPTION:
XS GIS Cut Line= 3
      2880755.70     10191153.11      2881479.00     10191275.00
      2881955.68     10191403.11
#Sta/Elev= 30
  4266.5  916.48  4294.2  916.44  4337.5  913.20  4354.7  910.91  4378.0  909.57
  4388.2  908.23  4438.9  905.70  4550.4  903.07  4611.3  903.49  4744.6  900.67
  4778.3  900.33  4838.8  898.27  4885.1  899.76  4925.7  898.03  4955.0  897.99
  4976.4  897.48  4995.8  893.60  5012.0  892.12  5013.8  890.88  5014.3  890.38
  5020.8  890.88  5038.0  900.37  5046.8  900.92  5079.4  900.60  5126.8  902.50
  5151.9  902.66  5206.7  901.07  5234.7  901.68  5382.1  909.60  5493.6  915.43
#Mann=6,-1,0
  4266.5    0.05       0  4744.6    0.12       0  4955.0    0.05       0
  5013.8    0.03       0  5020.8    0.05       0  5382.1    0.12       0
Bank Sta=5013.8,5020.8
Exp/Cntr=0.3,0.1

Type RM Length L Ch R = 1,11610,337,337,337
BEGIN DESCRIPTION:
MOSS CREEK 25.0
END DESCRIPTION:
XS GIS Cut Line= 3
      2880805.66     10191253.09      2881188.50     10191652.00
      2882005.65     10191453.12
#Sta/Elev= 30
  4447.1  909.85  4510.8  904.69  4715.9  900.40  4760.4  897.51  4765.5  895.35
  4779.7  894.59  4800.8  894.87  4814.9  897.06  4829.1  896.24  4843.2  894.33
  4850.2  890.83  4871.5  895.53  4885.7  895.39  4899.8  893.59  4902.9  891.82
  4906.8  889.60  4935.1  894.85  4942.3  892.39  4991.7  889.02  4993.6  887.75
  4994.1  887.25  5001.0  887.75  5014.5  893.33  5019.6  891.56  5025.2  893.38
  5079.4  895.80  5255.7  897.44  5449.9  900.29  5718.5  910.95  5841.0  917.14
#Mann=8,-1,0
  4447.1    0.05       0  4760.4    0.12       0  4902.9    0.05       0
  4993.6    0.05       0  5001.0    0.05       0  5025.2    0.12       0
  5255.7    0.05       0  5718.5    0.12       0
Bank Sta=4993.6,5001
Exp/Cntr=0.3,0.1

Type RM Length L Ch R = 1,11273,488,488,488
BEGIN DESCRIPTION:
MOSS CREEK 24.0
END DESCRIPTION:
XS GIS Cut Line= 3
      2880605.66     10191703.11      2881348.00     10191911.00
      2881755.67     10191803.12
#Sta/Elev= 30
  4229.1  913.10  4374.5  904.02  4393.0  904.11  4437.5  901.94  4644.5  896.93
  4768.4  895.69  4844.0  896.39  4878.1  894.88  4893.7  894.02  4904.1  891.39
  4912.2  886.65  4917.4  891.07  4924.9  887.63  4945.7  887.75  4947.8  885.84
  4948.3  885.34  4955.2  885.84  4959.3  886.16  5000.0  886.76  5018.3  889.61
  5047.3  891.17  5052.4  892.43  5080.4  890.91  5165.1  893.58  5193.7  895.14
  5208.2  895.26  5235.5  897.84  5266.6  898.20  5328.9  902.00  5421.7  905.59
#Mann=7,-1,0
  4229.1    0.05       0  4768.4    0.12       0  4947.8    0.05       0
  4955.2    0.12       0  4959.3    0.05       0  5165.1    0.12       0
  5193.7    0.05       0
Bank Sta=4947.8,4955.2
Exp/Cntr=0.3,0.1

Type RM Length L Ch R = 1,10785,468,468,468
BEGIN DESCRIPTION:
MOSS CREEK 23.0
END DESCRIPTION:
XS GIS Cut Line= 3
      2880705.67     10192403.11      2881348.75     10192345.00
      2881705.71     10192553.12
#Sta/Elev= 30
  4354.3  906.65  4364.4  906.75  4444.7  901.45  4565.2  895.88  4631.3  891.39
  4664.5  890.64  4742.0  889.26  4841.0  890.19  4940.5  890.13  4956.8  890.22
  4963.6  888.19  4968.6  889.12  4986.9  882.01  4992.2  881.87  4992.7  881.37
  4999.7  881.87  5004.2  885.02  5019.6  884.67  5025.7  886.15  5031.5  889.09
  5054.3  890.60  5121.6  891.98  5135.4  893.10  5148.9  891.30  5193.2  891.15
  5216.4  892.66  5266.4  892.52  5312.9  894.16  5383.3  897.13  5413.2  901.23
#Mann=8,-1,0
  4354.3    0.05       0  4664.5    0.12       0  4841.0    0.05       0
  4940.5    0.12       0  4992.2    0.07       0  4999.7    0.12       0
  5312.9    0.05       0  5383.3    0.12       0
Bank Sta=4992.2,4999.7
Exp/Cntr=0.3,0.1

Type RM Length L Ch R = 1,10317,496,496,496
BEGIN DESCRIPTION:
MOSS CREEK 22.0
END DESCRIPTION:
XS GIS Cut Line= 3
      2880705.67     10192453.11      2881401.50     10192760.00
      2881655.67     10192803.11
#Sta/Elev= 30
  4239.5  907.81  4381.6  898.46  4503.5  895.66  4602.2  895.05  4611.1  893.71
  4649.2  892.72  4676.1  892.23  4718.8  889.20  4755.1  890.61  4799.7  890.85
  4875.2  888.73  4893.0  883.05  4898.5  887.21  4906.2  882.91  4916.3  880.50
  4921.8  884.53  4928.1  881.33  4939.0  880.53  4950.6  881.61  4968.4  880.45
  4973.9  882.37  4982.7  881.19  5051.2  880.16  5051.7  879.66  5058.8  880.16
  5065.1  887.14  5109.5  887.50  5169.9  891.95  5197.0  896.03  5257.8  900.76
#Mann=6,-1,0
  4239.5    0.05       0  4649.2    0.12       0  4676.1    0.05       0
  4755.1    0.12       0  5051.2    0.07       0  5058.8    0.12       0
Bank Sta=5051.2,5058.8
Exp/Cntr=0.3,0.1

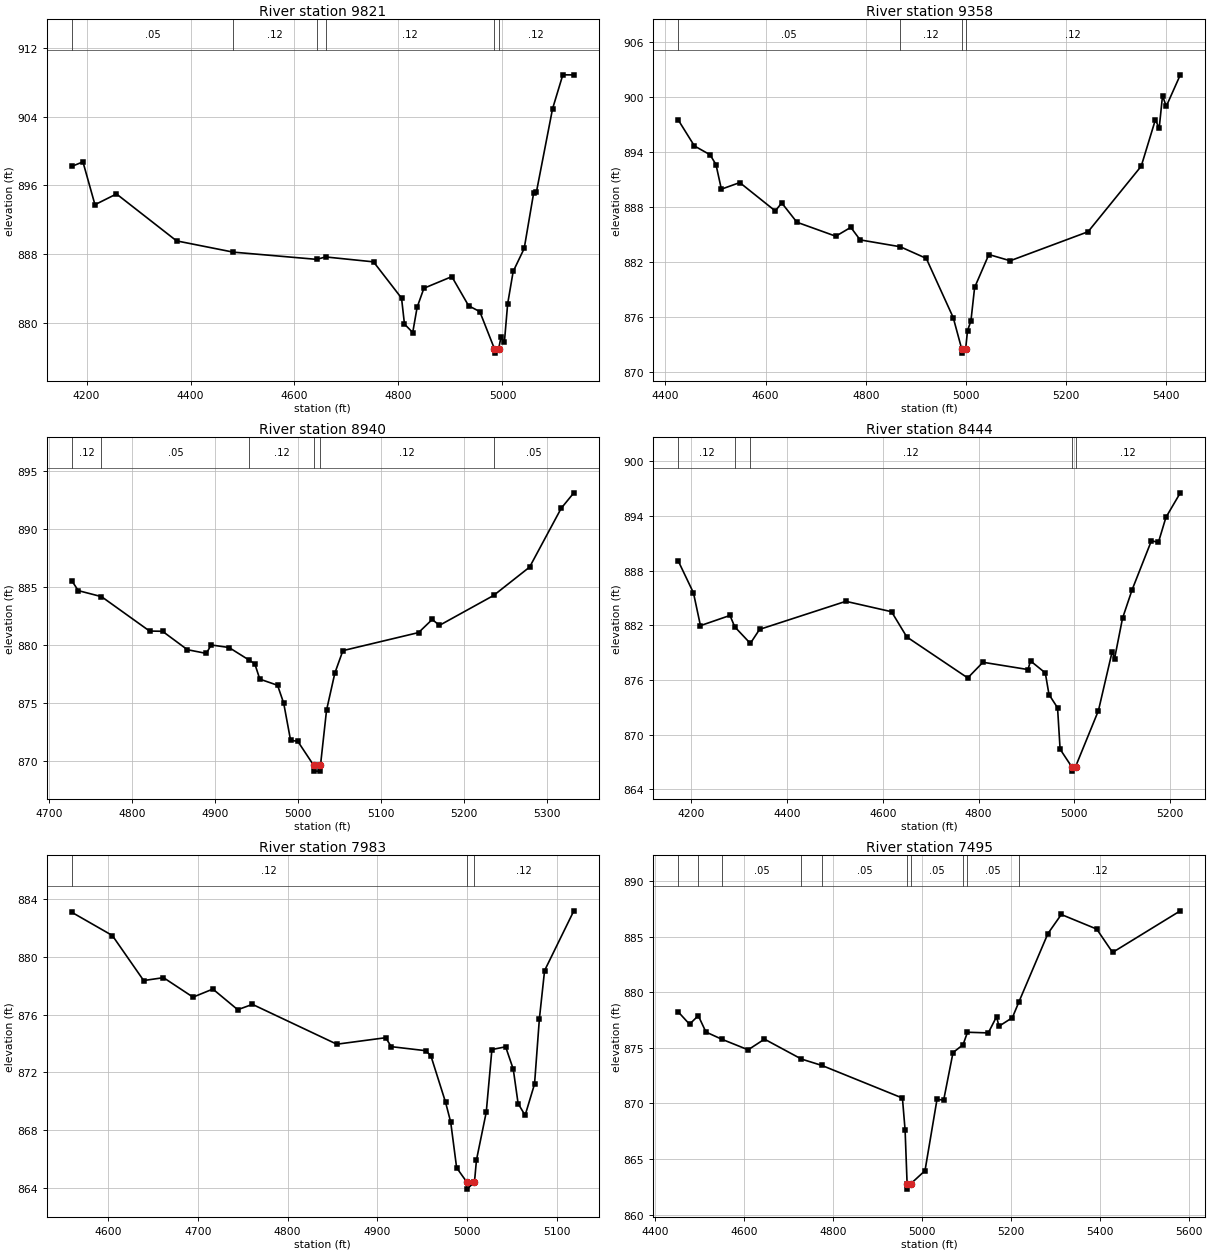
Type RM Length L Ch R = 1,9821,463,463,463
BEGIN DESCRIPTION:
MOSS CREEK 21.0
END DESCRIPTION:
XS GIS Cut Line= 3
      2880805.69     10193503.11      2881576.25     10193199.00
      2881705.66     10193153.12
#Sta/Elev= 30
  4171.6  898.21  4193.1  898.73  4216.2  893.75  4257.6  895.00  4373.2  889.54
  4482.2  888.23  4642.5  887.39  4659.9  887.67  4752.0  887.10  4805.9  882.88
  4811.5  879.86  4827.4  878.88  4835.9  881.82  4848.9  884.03  4902.6  885.38
  4934.9  881.99  4956.4  881.31  4984.6  876.98  4985.1  876.48  4992.7  876.98
  4997.0  878.30  5003.7  877.74  5010.0  882.22  5020.6  885.98  5041.8  888.66
  5060.1  895.15  5065.4  895.25  5096.3  904.90  5116.1  908.86  5137.3  908.85
#Mann=6,-1,0
  4171.6    0.05       0  4482.2    0.12       0  4642.5    0.05       0
  4659.9    0.12       0  4984.6    0.07       0  4992.7    0.12       0
Bank Sta=4984.6,4992.7
Exp/Cntr=0.3,0.1

Type RM Length L Ch R = 1,9358,418,418,418
BEGIN DESCRIPTION:
MOSS CREEK 20.0
END DESCRIPTION:
XS GIS Cut Line= 3
      2880955.67     10193853.12      2881489.25     10193641.00
      2881805.69     10193353.11
#Sta/Elev= 30
  4425.8  897.48  4458.1  894.64  4489.3  893.68  4501.1  892.61  4511.9  889.92
  4548.6  890.64  4619.5  887.54  4632.3  888.42  4662.6  886.31  4740.2  884.78
  4770.2  885.75  4788.8  884.38  4868.9  883.63  4920.8  882.36  4974.6  875.89
  4991.3  872.51  4991.8  872.01  4999.5  872.51  5003.1  874.47  5009.9  875.52
  5017.3  879.18  5045.7  882.78  5088.3  882.10  5243.7  885.27  5349.8  892.43
  5378.1  897.51  5385.6  896.56  5392.3  900.12  5399.8  898.97  5427.8  902.41
#Mann=4,-1,0
  4425.8    0.05       0  4868.9    0.12       0  4991.3    0.07       0
  4999.5    0.12       0
Bank Sta=4991.3,4999.5
Exp/Cntr=0.3,0.1

Type RM Length L Ch R = 1,8940,496,496,496
BEGIN DESCRIPTION:
MOSS CREEK 19.0
END DESCRIPTION:
XS GIS Cut Line= 3
      2881505.69     10194103.11      2881740.25     10193965.00
      2881855.70     10193653.08
#Sta/Elev= 30
  4727.8  885.54  4735.6  884.68  4763.6  884.16  4821.5  881.19  4837.1  881.17
  4867.1  879.58  4889.9  879.26  4895.7  879.99  4917.2  879.77  4941.5  878.68
  4948.3  878.36  4954.3  877.04  4975.7  876.51  4983.1  874.96  4991.4  871.75
  5000.0  871.68  5019.2  869.60  5019.7  869.10  5026.9  869.10  5027.4  869.60
  5034.7  874.36  5044.7  877.56  5054.4  879.50  5145.6  881.06  5162.0  882.19
  5170.7  881.68  5235.9  884.26  5279.3  886.71  5317.4  891.79  5332.6  893.12
#Mann=6,-1,0
  4727.8    0.12       0  4763.6    0.05       0  4941.5    0.12       0
  5019.2    0.07       0  5027.4    0.12       0  5235.9    0.05       0
Bank Sta=5019.2,5027.4
Exp/Cntr=0.3,0.1

Type RM Length L Ch R = 1,8444,461,461,461
BEGIN DESCRIPTION:
MOSS CREEK 18.0
END DESCRIPTION:
XS GIS Cut Line= 3
      2881355.68     10194453.11      2882135.75     10194177.00
      2882355.66     10194153.11
#Sta/Elev= 30
  4172.5  889.06  4204.3  885.56  4218.9  881.96  4280.6  883.08  4290.5  881.83
  4323.1  880.01  4342.4  881.55  4522.6  884.63  4618.0  883.49  4649.9  880.72
  4777.2  876.22  4809.0  877.94  4903.0  877.14  4908.3  878.09  4939.2  876.77
  4946.9  874.40  4964.8  872.94  4970.1  868.40  4994.1  866.49  4994.6  865.99
  5002.5  866.49  5050.2  872.64  5078.8  879.10  5083.9  878.35  5100.5  882.77
  5120.6  885.91  5160.9  891.29  5175.4  891.09  5191.1  893.84  5221.2  896.54
#Mann=5,-1,0
  4172.5    0.12       0  4290.5    0.05       0  4323.1    0.12       0
  4994.1    0.07       0  5002.5    0.12       0
Bank Sta=4994.1,5002.5
Exp/Cntr=0.3,0.1

Type RM Length L Ch R = 1,7983,488,488,488
BEGIN DESCRIPTION:
MOSS CREEK 17.0
END DESCRIPTION:
XS GIS Cut Line= 3
      2881755.65     10194403.09      2882146.00     10194607.00
      2882255.70     10194653.12
#Sta/Elev= 30
  4559.6  883.09  4604.8  881.48  4639.7  878.36  4661.8  878.56  4694.7  877.21
  4716.8  877.77  4744.5  876.34  4760.9  876.71  4854.9  873.95  4909.4  874.40
  4915.5  873.78  4954.0  873.50  4959.7  873.15  4976.1  869.92  4981.8  868.55
  4988.4  865.39  4999.6  864.41  5000.1  863.91  5008.3  864.41  5010.5  865.93
  5021.4  869.24  5027.7  873.58  5043.0  873.77  5051.5  872.22  5056.9  869.84
  5064.7  869.02  5075.2  871.19  5080.6  875.71  5086.4  879.05  5119.0  883.19
#Mann=3,-1,0
  4559.6    0.12       0  4999.6    0.07       0  5008.3    0.12       0
Bank Sta=4999.6,5008.3
Exp/Cntr=0.3,0.1

Type RM Length L Ch R = 1,7495,214,214,214
BEGIN DESCRIPTION:
Mapping XS cd000ddc
END DESCRIPTION:
XS GIS Cut Line= 4
      2881517.24     10194476.76      2881670.04     10194726.79
      2881899.20     10195060.13      2882301.31     10195212.65
#Sta/Elev= 30
  4452.3  878.23  4477.7  877.12  4497.3  877.89  4514.5  876.42  4549.6  875.78
  4609.3  874.82  4646.0  875.78  4728.9  873.99  4775.2  873.41  4955.8  870.48
  4961.8  867.60  4966.3  862.79  4966.8  862.29  4975.0  862.79  5006.5  863.95
  5033.5  870.37  5048.4  870.29  5069.4  874.57  5092.0  875.28  5101.9  876.40
  5148.6  876.34  5167.2  877.80  5172.6  876.94  5202.7  877.71  5217.1  879.10
  5282.5  885.27  5312.6  886.99  5392.1  885.68  5427.8  883.58  5579.9  887.32
#Mann=10,-1,0
  4452.3    0.05       0  4497.3    0.12       0  4549.6    0.05       0
  4728.9    0.12       0  4775.2    0.05       0  4966.3    0.05       0
  4975.0    0.05       0  5092.0    0.12       0  5101.9    0.05       0
  5217.1    0.12       0
Bank Sta=4966.3,4975
Exp/Cntr=0.3,0.1