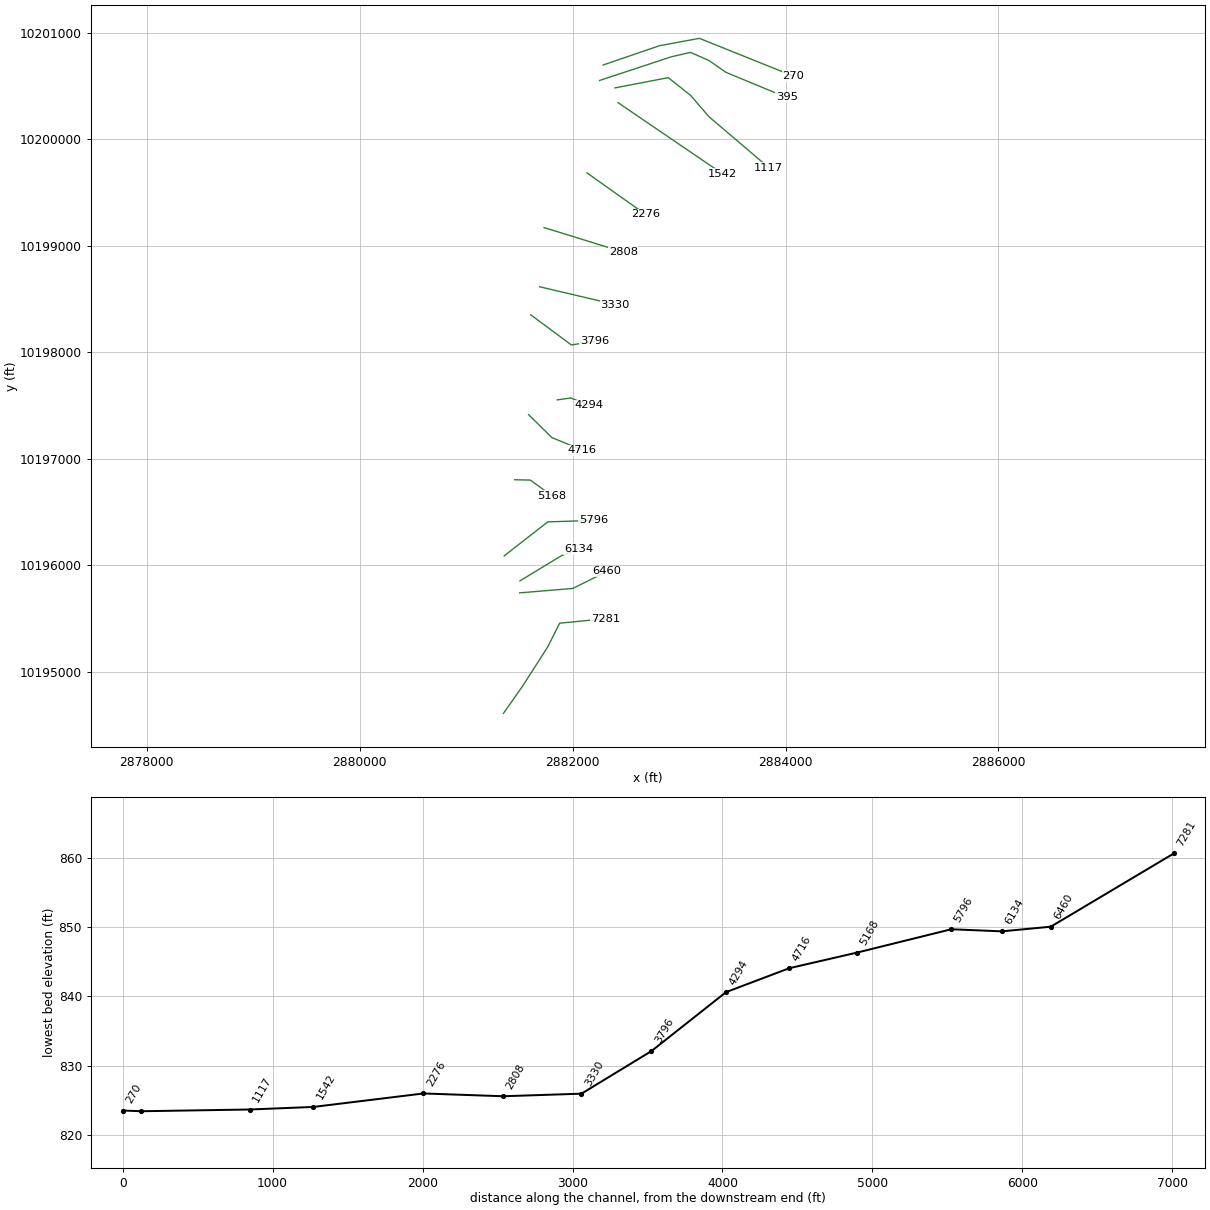
HEC-RAS study MOSS CREEK.prj: MOSS CREEK Base Level Engineering

--- MOSS CREEK.g01 (geometry) --- (continued)

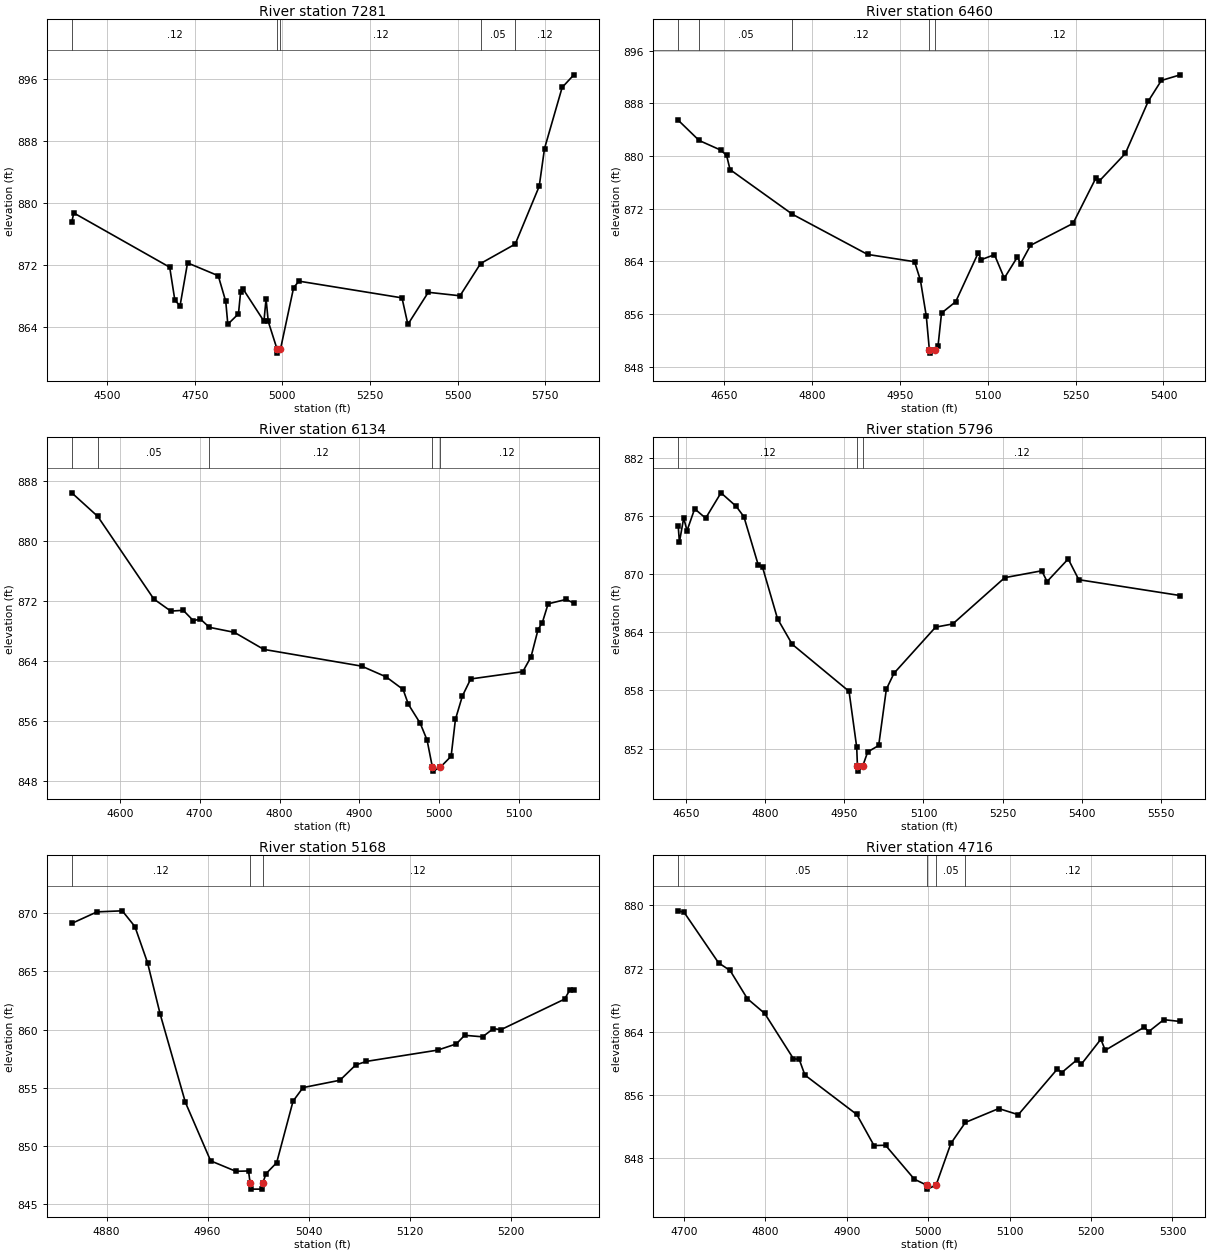
Type RM Length L Ch R = 1,7281,821,821,821
BEGIN DESCRIPTION:
Mapping XS 04219516
END DESCRIPTION:
XS GIS Cut Line= 5
      2881350.58     10194608.73      2881531.15     10194865.68
      2881767.26     10195233.74      2881878.37     10195455.96
      2882308.97     10195497.63
#Sta/Elev= 30
  4399.1  877.55  4404.9  878.71  4678.5  871.70  4693.3  867.41  4708.1  866.73
  4729.4  872.26  4817.0  870.60  4838.4  867.28  4844.3  864.33  4874.7  865.68
  4880.7  868.46  4888.3  868.85  4947.4  864.72  4953.4  867.62  4959.6  864.70
  4984.9  861.10  4985.4  860.60  4994.5  861.10  5032.0  869.06  5047.2  869.90
  5341.2  867.74  5358.0  864.31  5416.2  868.46  5506.7  868.01  5565.5  872.18
  5664.3  874.69  5732.7  882.16  5747.8  887.03  5798.1  894.93  5831.5  896.56
#Mann=5,-1,0
  4399.1    0.12       0  4984.9    0.07       0  4994.5    0.12       0
  5565.5    0.05       0  5664.3    0.12       0
Bank Sta=4984.9,4994.5
Exp/Cntr=0.3,0.1

Type RM Length L Ch R = 1,6460,326,326,326
BEGIN DESCRIPTION:
Mapping XS 1b271955
END DESCRIPTION:
XS GIS Cut Line= 3
      2881503.37     10195740.68      2882003.37     10195782.35
      2882321.75     10195941.54
#Sta/Elev= 30
  4571.1  885.43  4606.7  882.36  4643.7  880.89  4653.7  880.09  4659.6  877.93
  4766.2  871.14  4894.5  865.04  4974.8  863.93  4984.8  861.13  4994.9  855.64
  5000.1  850.54  5000.6  850.04  5009.8  850.54  5014.9  851.12  5020.9  856.13
  5045.1  857.85  5083.4  865.24  5089.0  864.25  5111.3  865.00  5128.1  861.43
  5150.4  864.63  5156.0  863.65  5172.8  866.41  5245.5  869.75  5284.6  876.65
  5290.2  876.17  5334.9  880.38  5374.1  888.33  5396.4  891.47  5428.8  892.33
#Mann=5,-1,0
  4571.1    0.12       0  4606.7    0.05       0  4766.2    0.12       0
  5000.1    0.07       0  5009.8    0.12       0
Bank Sta=5000.1,5009.8
Exp/Cntr=0.3,0.1

Type RM Length L Ch R = 1,6134,338,338,338
BEGIN DESCRIPTION:
MOSS CREEK 13.0
END DESCRIPTION:
XS GIS Cut Line= 3
      2881505.65     10195853.09      2881898.75     10196092.00
      2882055.67     10196153.11
#Sta/Elev= 30
  4540.0  886.45  4572.5  883.31  4642.7  872.30  4664.0  870.69  4679.5  870.80
  4692.2  869.41  4700.9  869.64  4712.2  868.53  4743.5  867.86  4780.3  865.59
  4902.8  863.36  4933.4  861.93  4954.7  860.25  4961.3  858.27  4976.1  855.75
  4984.7  853.51  4991.4  849.87  4991.9  849.37  5001.1  849.87  5014.8  851.35
  5020.2  856.27  5028.9  859.38  5039.3  861.65  5104.5  862.62  5114.8  864.59
  5123.6  868.23  5129.0  869.17  5136.2  871.66  5158.8  872.25  5168.4  871.75
#Mann=5,-1,0
  4540.0    0.12       0  4572.5    0.05       0  4712.2    0.12       0
  4991.4    0.07       0  5001.1    0.12       0
Bank Sta=4991.4,5001.1
Exp/Cntr=0.3,0.1

Type RM Length L Ch R = 1,5796,628,628,628
BEGIN DESCRIPTION:
Mapping XS 8ca00213
END DESCRIPTION:
XS GIS Cut Line= 3
      2881357.52     10196087.89      2881767.26     10196407.35
      2882197.77     10196421.24
#Sta/Elev= 30
  4635.8  874.95  4638.0  873.31  4646.1  875.80  4652.5  874.51  4666.9  876.76
  4687.7  875.79  4716.7  878.41  4745.6  877.01  4760.1  875.94  4787.3  870.95
  4795.4  870.72  4823.7  865.41  4851.5  862.77  4959.1  857.91  4973.6  852.14
  4975.0  850.17  4975.5  849.67  4984.8  850.17  4994.4  851.65  5015.2  852.32
  5029.7  858.13  5044.2  859.78  5122.9  864.54  5155.4  864.87  5253.8  869.65
  5323.9  870.36  5333.9  869.25  5373.9  871.58  5393.9  869.44  5586.1  867.80
#Mann=3,-1,0
  4635.8    0.12       0  4975.0    0.07       0  4984.8    0.12       0
Bank Sta=4975,4984.8
Exp/Cntr=0.3,0.1

Type RM Length L Ch R = 1,5168,452,452,452
BEGIN DESCRIPTION:
MOSS CREEK 11.0
END DESCRIPTION:
XS GIS Cut Line= 3
      2881455.68     10196803.11      2881603.25     10196800.00
      2881805.67     10196653.12
#Sta/Elev= 30
  4852.4  869.13  4872.4  870.12  4892.4  870.21  4902.4  868.86  4912.4  865.76
  4922.4  861.35  4942.4  853.76  4962.4  848.74  4982.4  847.84  4992.4  847.87
  4993.7  846.81  4994.2  846.31  5003.2  846.31  5003.7  846.81  5006.2  847.63
  5014.7  848.58  5027.7  853.87  5035.6  855.03  5064.8  855.66  5077.3  856.97
  5085.8  857.28  5142.3  858.25  5157.0  858.78  5163.6  859.52  5177.8  859.39
  5186.3  860.09  5192.5  860.01  5242.8  862.63  5247.0  863.43  5250.1  863.43
#Mann=3,-1,0
  4852.4    0.12       0  4993.7    0.07       0  5003.7    0.12       0
Bank Sta=4993.7,5003.7
Exp/Cntr=0.3,0.1

Type RM Length L Ch R = 1,4716,422,422,422
BEGIN DESCRIPTION:
MOSS CREEK 10.0
END DESCRIPTION:
XS GIS Cut Line= 3
      2881586.73     10197414.27      2881805.75     10197199.00
      2882092.21     10197081.55
#Sta/Elev= 30
  4692.9  879.32  4700.1  879.13  4742.5  872.72  4756.6  871.76  4777.8  868.19
  4799.1  866.32  4834.4  860.58  4841.5  860.50  4848.5  858.51  4912.2  853.52
  4933.4  849.58  4947.5  849.62  4982.9  845.32  4998.1  844.56  4998.6  844.06
  5009.6  844.56  5027.8  849.85  5045.6  852.51  5086.6  854.27  5110.6  853.49
  5158.6  859.28  5164.0  858.83  5182.6  860.44  5188.0  859.88  5212.0  863.05
  5217.4  861.65  5265.3  864.58  5270.7  864.01  5289.3  865.53  5309.6  865.30
#Mann=4,-1,0
  4692.9    0.05       0  4998.1    0.05       0  5009.6    0.05       0
  5045.6    0.12       0
Bank Sta=4998.1,5009.6
Exp/Cntr=0.3,0.1

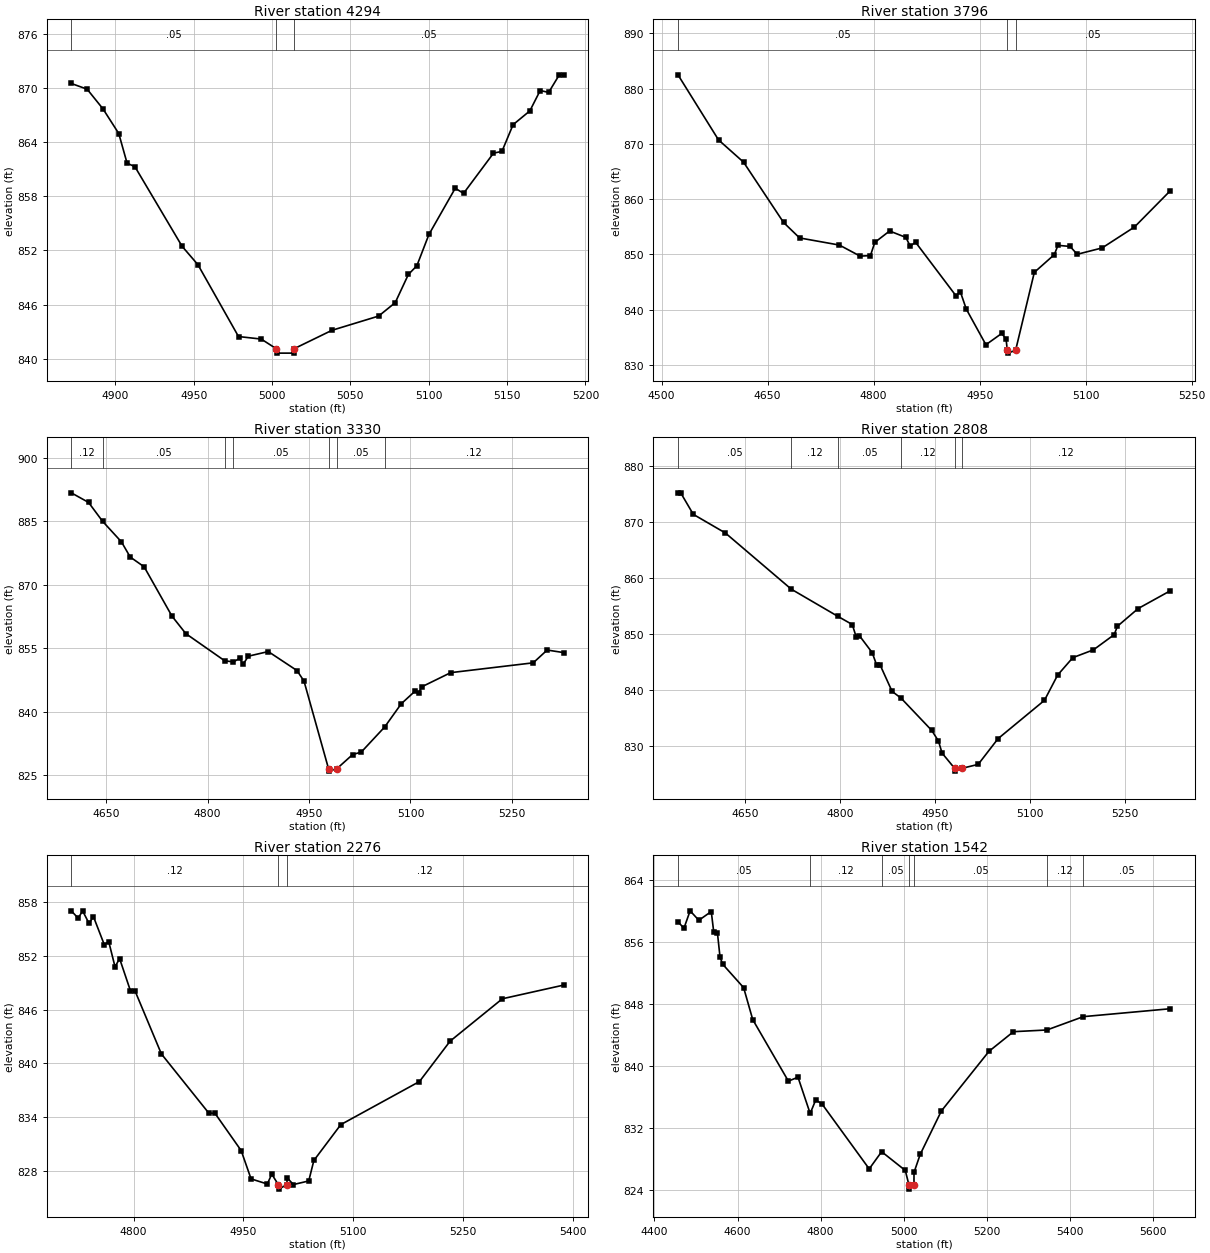
Type RM Length L Ch R = 1,4294,498,498,498
BEGIN DESCRIPTION:
MOSS CREEK 9.0
END DESCRIPTION:
XS GIS Cut Line= 3
      2881855.66     10197553.11      2881982.50     10197571.00
      2882155.67     10197503.12
#Sta/Elev= 30
  4871.9  870.52  4882.0  869.89  4892.1  867.71  4902.2  864.97  4907.5  861.68
  4912.5  861.29  4942.6  852.46  4952.7  850.42  4978.6  842.45  4993.1  842.17
  5002.6  841.11  5003.1  840.61  5013.7  840.61  5014.2  841.11  5038.2  843.14
  5068.0  844.72  5078.6  846.21  5087.0  849.34  5092.4  850.30  5100.1  853.77
  5116.9  858.90  5122.2  858.33  5141.3  862.79  5146.7  862.99  5153.8  865.95
  5164.5  867.48  5171.1  869.74  5176.5  869.53  5183.3  871.48  5186.0  871.48
#Mann=3,-1,0
  4871.9    0.05       0  5002.6    0.05       0  5014.2    0.05       0
Bank Sta=5002.6,5014.2
Exp/Cntr=0.3,0.1

Type RM Length L Ch R = 1,3796,466,466,466
BEGIN DESCRIPTION:
MOSS CREEK 8.0
END DESCRIPTION:
XS GIS Cut Line= 3
      2881605.71     10198353.10      2881988.75     10198069.00
      2882205.68     10198103.11
#Sta/Elev= 30
  4523.1  882.51  4580.5  870.72  4615.9  866.69  4672.5  855.77  4695.2  852.97
  4751.5  851.68  4780.8  849.68  4795.4  849.77  4801.6  852.16  4822.5  854.23
  4845.5  853.07  4851.7  851.48  4859.2  852.20  4916.4  842.50  4922.6  843.23
  4931.0  840.09  4958.8  833.63  4981.1  835.67  4987.3  834.67  4989.1  832.61
  4989.6  832.11  5000.8  832.61  5027.3  846.74  5055.6  849.95  5060.7  851.63
  5077.9  851.43  5088.0  850.01  5123.2  851.16  5169.0  854.95  5219.6  861.51
#Mann=3,-1,0
  4523.1    0.05       0  4989.1    0.05       0  5000.8    0.05       0
Bank Sta=4989.1,5000.8
Exp/Cntr=0.3,0.1

Type RM Length L Ch R = 1,3330,522,522,522
BEGIN DESCRIPTION:
Mapping XS e9deb862
END DESCRIPTION:
XS GIS Cut Line= 2
      2881690.86     10198615.69      2882399.21     10198449.01
#Sta/Elev= 30
  4598.6  891.71  4624.1  889.45  4644.8  885.00  4672.8  880.12  4685.7  876.55
  4706.3  874.24  4747.4  862.60  4767.9  858.46  4825.4  852.04  4838.3  851.78
  4847.5  852.62  4852.6  851.21  4860.4  853.13  4889.8  854.22  4932.2  849.74
  4942.6  847.26  4979.0  826.48  4979.5  825.98  4990.7  826.48  5014.5  829.89
  5027.3  830.48  5061.9  836.41  5086.4  841.89  5106.9  844.89  5112.0  844.50
  5117.2  845.93  5159.5  849.24  5281.5  851.56  5302.1  854.58  5326.3  853.98
#Mann=7,-1,0
  4598.6    0.12       0  4644.8    0.05       0  4825.4    0.12       0
  4838.3    0.05       0  4979.0    0.05       0  4990.7    0.05       0
  5061.9    0.12       0
Bank Sta=4979,4990.7
Exp/Cntr=0.3,0.1

Type RM Length L Ch R = 1,2808,532,532,532
BEGIN DESCRIPTION:
Mapping XS 2f3174dc
END DESCRIPTION:
XS GIS Cut Line= 2
      2881732.54     10199171.24      2882475.61     10198942.07
#Sta/Elev= 30
  4543.9  875.15  4548.2  875.15  4568.1  871.32  4618.8  868.00  4722.9  858.00
  4796.2  853.18  4819.3  851.70  4825.2  849.56  4830.5  849.72  4850.7  846.70
  4857.9  844.45  4863.1  844.53  4882.1  839.81  4896.4  838.59  4944.8  832.85
  4955.3  830.98  4961.1  828.82  4980.9  826.11  4981.4  825.61  4992.6  826.11
  5018.1  826.81  5049.5  831.39  5122.8  838.21  5143.7  842.72  5167.6  845.81
  5200.2  847.20  5232.9  849.90  5238.1  851.40  5270.8  854.55  5321.5  857.71
#Mann=6,-1,0
  4543.9    0.05       0  4722.9    0.12       0  4796.2    0.05       0
  4896.4    0.12       0  4980.9    0.07       0  4992.6    0.12       0
Bank Sta=4980.9,4992.6
Exp/Cntr=0.3,0.1

Type RM Length L Ch R = 1,2276,734,734,734
BEGIN DESCRIPTION:
Mapping XS 1242c77f
END DESCRIPTION:
XS GIS Cut Line= 2
      2882135.29     10199685.14      2882683.93     10199296.23
#Sta/Elev= 30
  4714.9  856.99  4724.3  856.17  4730.4  856.98  4739.1  855.60  4745.2  856.34
  4760.0  853.22  4766.1  853.55  4774.7  850.75  4780.9  851.68  4795.6  848.12
  4801.8  848.11  4838.0  841.06  4902.7  834.48  4911.3  834.44  4947.0  830.30
  4960.5  827.15  4982.7  826.58  4988.8  827.68  4997.7  826.51  4998.2  826.01
  5009.5  826.51  5009.7  827.27  5018.4  826.52  5039.3  826.92  5046.3  829.20
  5083.1  833.19  5190.6  837.99  5232.4  842.48  5303.8  847.20  5387.4  848.72
#Mann=3,-1,0
  4714.9    0.12       0  4997.7    0.07       0  5009.5    0.12       0
Bank Sta=4997.7,5009.5
Exp/Cntr=0.3,0.1

Type RM Length L Ch R = 1,1542,425,425,425
BEGIN DESCRIPTION:
Mapping XS 5329a3e8
END DESCRIPTION:
XS GIS Cut Line= 2
      2882426.95     10200344.87      2883406.14     10199678.19
#Sta/Elev= 30
  4456.6  858.58  4470.9  857.71  4485.8  859.97  4506.8  858.75  4536.7  859.88
  4542.7  857.22  4551.6  857.10  4557.7  854.04  4563.9  853.10  4614.6  850.06
  4636.5  845.94  4722.3  838.00  4745.4  838.51  4774.7  833.83  4788.1  835.57
  4803.0  835.07  4916.8  826.68  4946.7  828.90  5003.6  826.48  5012.6  824.57
  5013.1  824.07  5024.5  824.57  5024.6  826.22  5039.5  828.55  5090.4  834.15
  5205.1  841.85  5263.9  844.38  5344.4  844.60  5432.0  846.32  5641.2  847.34
#Mann=7,-1,0
  4456.6    0.05       0  4774.7    0.12       0  4946.7    0.05       0
  5012.6    0.03       0  5024.5    0.05       0  5344.4    0.12       0
  5432.0    0.05       0
Bank Sta=5012.6,5024.5
Exp/Cntr=0.3,0.1

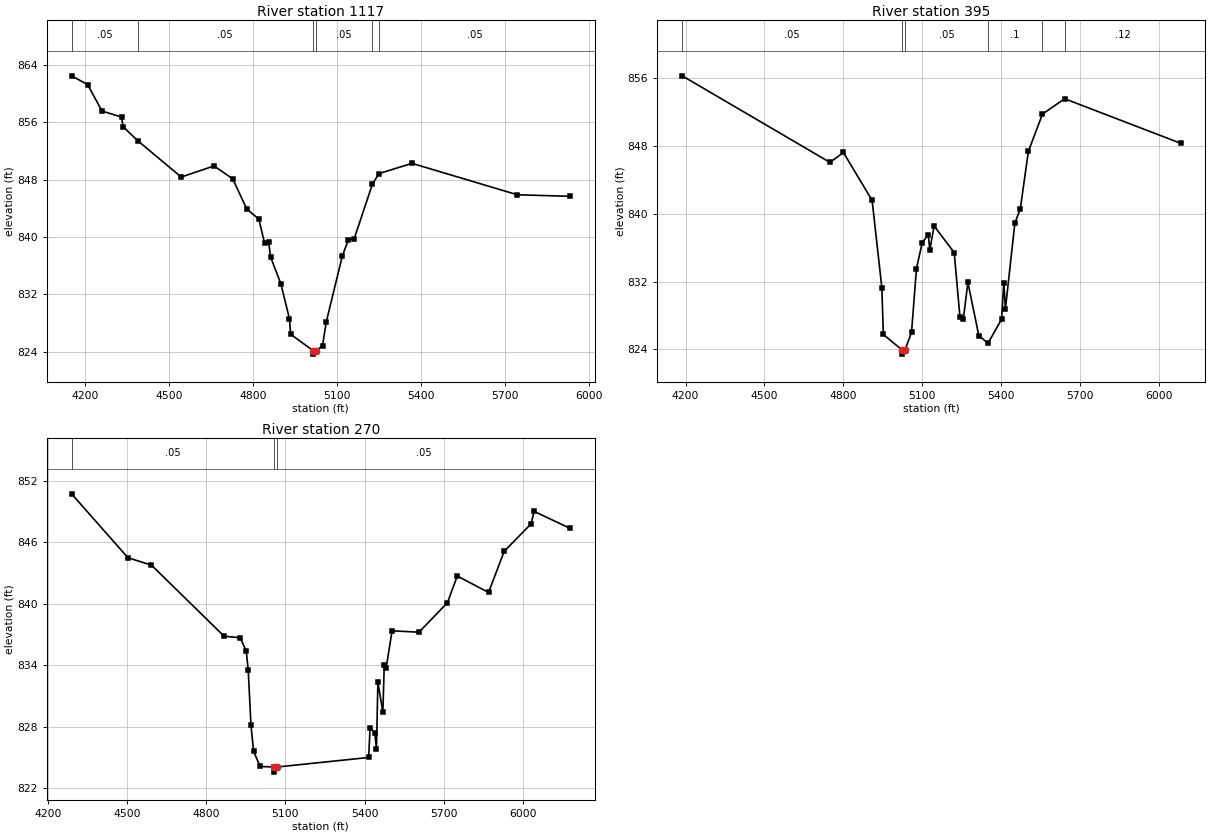
Type RM Length L Ch R = 1,1117,722,722,722
BEGIN DESCRIPTION:
Mapping XS ac5c68d1
END DESCRIPTION:
XS GIS Cut Line= 5
      2882399.19     10200483.74      2882898.14     10200579.61
      2883107.54     10200414.29      2883281.15     10200212.91
      2883842.14     10199735.02
#Sta/Elev= 30
  4152.9  862.43  4210.4  861.20  4261.3  857.53  4331.3  856.69  4336.4  855.36
  4388.6  853.41  4544.2  848.34  4661.0  849.89  4727.9  848.09  4777.6  843.91
  4820.9  842.49  4841.7  839.10  4856.2  839.27  4862.6  837.24  4899.5  833.49
  4930.2  828.61  4934.3  826.47  5013.9  824.20  5014.4  823.70  5025.8  824.20
  5048.1  824.86  5061.5  828.19  5118.6  837.33  5140.5  839.64  5161.3  839.78
  5225.8  847.32  5249.3  848.82  5367.2  850.25  5742.8  845.88  5930.6  845.66
#Mann=6,-1,0
  4152.9    0.05       0  4388.6    0.05       0  5013.9    0.05       0
  5025.8    0.05       0  5225.8    0.12       0  5249.3    0.05       0
Bank Sta=5013.9,5025.8
Exp/Cntr=0.3,0.1

Type RM Length L Ch R = 1,395,125,125,125
BEGIN DESCRIPTION:
Mapping XS ee04a120
END DESCRIPTION:
XS GIS Cut Line= 6
      2882253.36     10200553.18      2882926.98     10200775.41
      2883107.54     10200817.07      2883281.15     10200740.68
      2883440.87     10200629.57      2884010.29     10200393.47
#Sta/Elev= 30
  4187.3  856.24  4749.4  846.04  4800.5  847.21  4909.7  841.56  4946.6  831.30
  4952.4  825.77  5022.8  823.95  5023.3  823.45  5034.7  823.95  5059.5  826.00
  5078.4  833.53  5100.2  836.58  5123.6  837.54  5129.0  835.70  5145.5  838.55
  5221.9  835.42  5243.8  827.80  5256.7  827.61  5273.9  831.90  5315.5  825.63
  5350.4  824.73  5401.9  827.54  5410.6  831.87  5416.7  828.79  5452.5  838.87
  5473.4  840.59  5503.9  847.33  5557.6  851.73  5641.9  853.54  6082.6  848.30
#Mann=6,-1,0
  4187.3    0.05       0  5022.8    0.03       0  5034.7    0.05       0
  5350.4     0.1       0  5557.6    0.05       0  5641.9    0.12       0
Bank Sta=5022.8,5034.7
Exp/Cntr=0.3,0.1

Type RM Length L Ch R = 1,270,0,0,0
BEGIN DESCRIPTION:
MOSS CREEK 1.0
END DESCRIPTION:
XS GIS Cut Line= 4
      2882288.09     10200699.02      2882815.87     10200879.57
      2883190.87     10200949.02      2884071.71     10200595.29
#Sta/Elev= 30
  4289.9  850.70  4503.7  844.46  4592.3  843.75  4867.9  836.81  4928.9  836.66
  4951.9  835.35  4959.4  833.47  4969.6  828.17  4979.7  825.57  5004.8  824.10
  5056.8  824.05  5057.3  823.55  5068.7  824.05  5415.7  824.98  5421.1  827.90
  5439.0  827.38  5445.3  825.81  5450.7  832.32  5469.5  829.41  5474.9  834.03
  5482.1  833.72  5504.5  837.34  5606.6  837.20  5714.2  840.08  5751.5  842.68
  5870.1  841.08  5929.3  845.09  6031.4  847.78  6042.5  848.99  6178.3  847.34
#Mann=3,-1,0
  4289.9    0.05       0  5056.8    0.03       0  5068.7    0.05       0
Bank Sta=5056.8,5068.7
Exp/Cntr=0.3,0.1

Chan Stop Cuts=-1