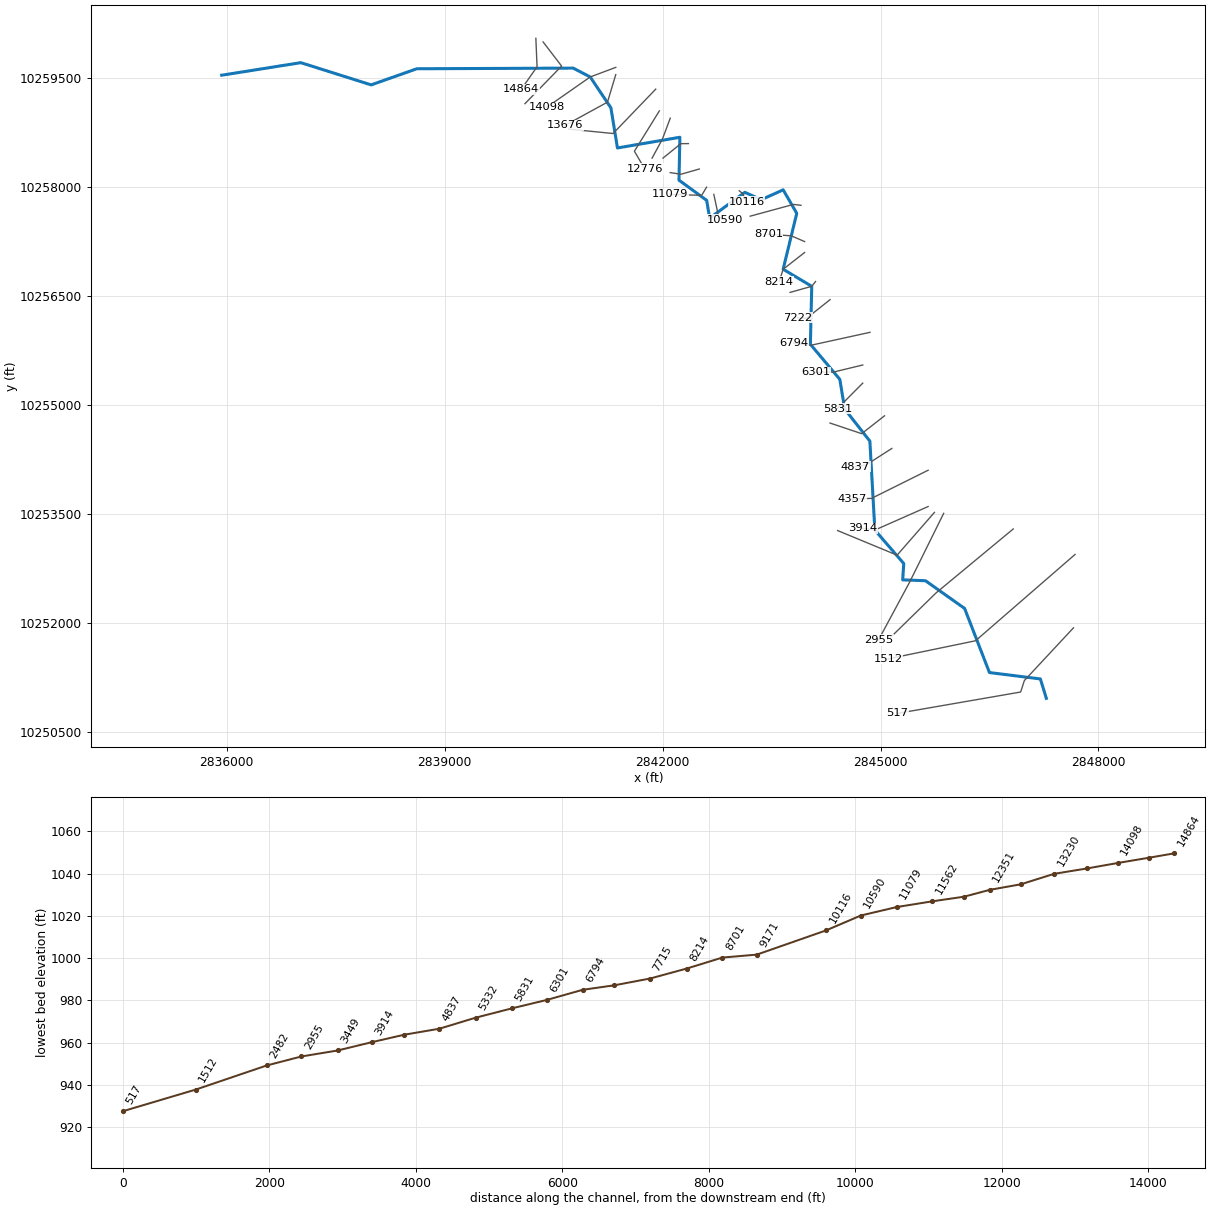
--- MUD CREEK.prj (project) ---

Proj Title=MUD CREEK Base Level Engineering
Current Plan=p01
Default Exp/Contr=0.3,0.1
English Units
Geom File=g01
Flow File=f01
Plan File=p01
BEGIN DESCRIPTION:
MUD CREEK
END DESCRIPTION:

--- MUD CREEK.p01 (plan) ---

Plan Title=Multiple Run
Short Identifier=Multiple
Geom File=g01
Flow File=f01
Subcritical Flow
K Sum by GR= 0
Std Step Tol= 0.01
Critical Tol= 0.01
Num of Std Step Trials= 20
Max Error Tol= 0.3
Flow Tol Ratio= 0.001
Split Flow NTrial= 30
Split Flow Tol= 0.02
Split Flow Ratio= 0.02
Log Output Level= 0
Friction Slope Method= 1
Unsteady Friction Slope Method= 2
Unsteady Bridges Friction Slope Method= 1
Parabolic Critical Depth
Global Vel Dist=  1 , 1 , 1
Global Log Level= 0
CheckData=True
Encroach Param= -1, 0, 0, 0
BEGIN DESCRIPTION:
Multiple Run
END DESCRIPTION:

--- MUD CREEK.f01 (steady flow) ---

Flow Title=Multiple
Number of Profiles=7
Profile Names=10-year,25-year,50-year,1pct_min,100-year,1pct_plu,500-year
River Rch & RM= MUD CREEK,Reach-1,14864
      68     132     206     107     323     977     854
River Rch & RM= MUD CREEK,Reach-1,6794
     105     217     349     186     560    1692    1540
Boundary for River Rch & Prof#=MUD CREEK,Reach-1,1
Up Type=0
Dn Type=3
Dn Slope=0.005
Boundary for River Rch & Prof#=MUD CREEK,Reach-1,2
Up Type=0
Dn Type=3
Dn Slope=0.005
Boundary for River Rch & Prof#=MUD CREEK,Reach-1,3
Up Type=0
Dn Type=3
Dn Slope=0.005
Boundary for River Rch & Prof#=MUD CREEK,Reach-1,4
Up Type=0
Dn Type=3
Dn Slope=0.005
Boundary for River Rch & Prof#=MUD CREEK,Reach-1,5
Up Type=0
Dn Type=3
Dn Slope=0.005
Boundary for River Rch & Prof#=MUD CREEK,Reach-1,6
Up Type=0
Dn Type=3
Dn Slope=0.005
Boundary for River Rch & Prof#=MUD CREEK,Reach-1,7
Up Type=0
Dn Type=3
Dn Slope=0.005

--- MUD CREEK.g01 (geometry) ---

Geom Title=Existing Conditions

River Reach=MUD CREEK,Reach-1
Reach XY= 30
      2835930.50     10259545.00      2837019.75     10259718.00
      2837988.50     10259412.00      2838616.50     10259634.00
      2840769.75     10259643.00      2841004.00     10259521.00
      2841288.50     10259096.00      2841379.00     10258543.00
      2842238.50     10258690.00      2842226.00     10258099.00
      2842607.25     10257821.00      2842648.25     10257576.00
      2843131.75     10257932.00      2843358.25     10257830.00
      2843660.25     10257966.00      2843847.25     10257642.00
      2843659.75     10256872.00      2844053.50     10256637.00
      2844034.75     10255839.00      2844440.00     10255355.00
      2844506.75     10254946.00      2844853.75     10254504.00
      2844922.25     10253279.00      2845320.25     10252818.00
      2845305.50     10252593.00      2845619.25     10252581.00
      2846158.00     10252199.00      2846499.75     10251316.00
      2847201.00     10251228.00      2847282.75     10250961.00

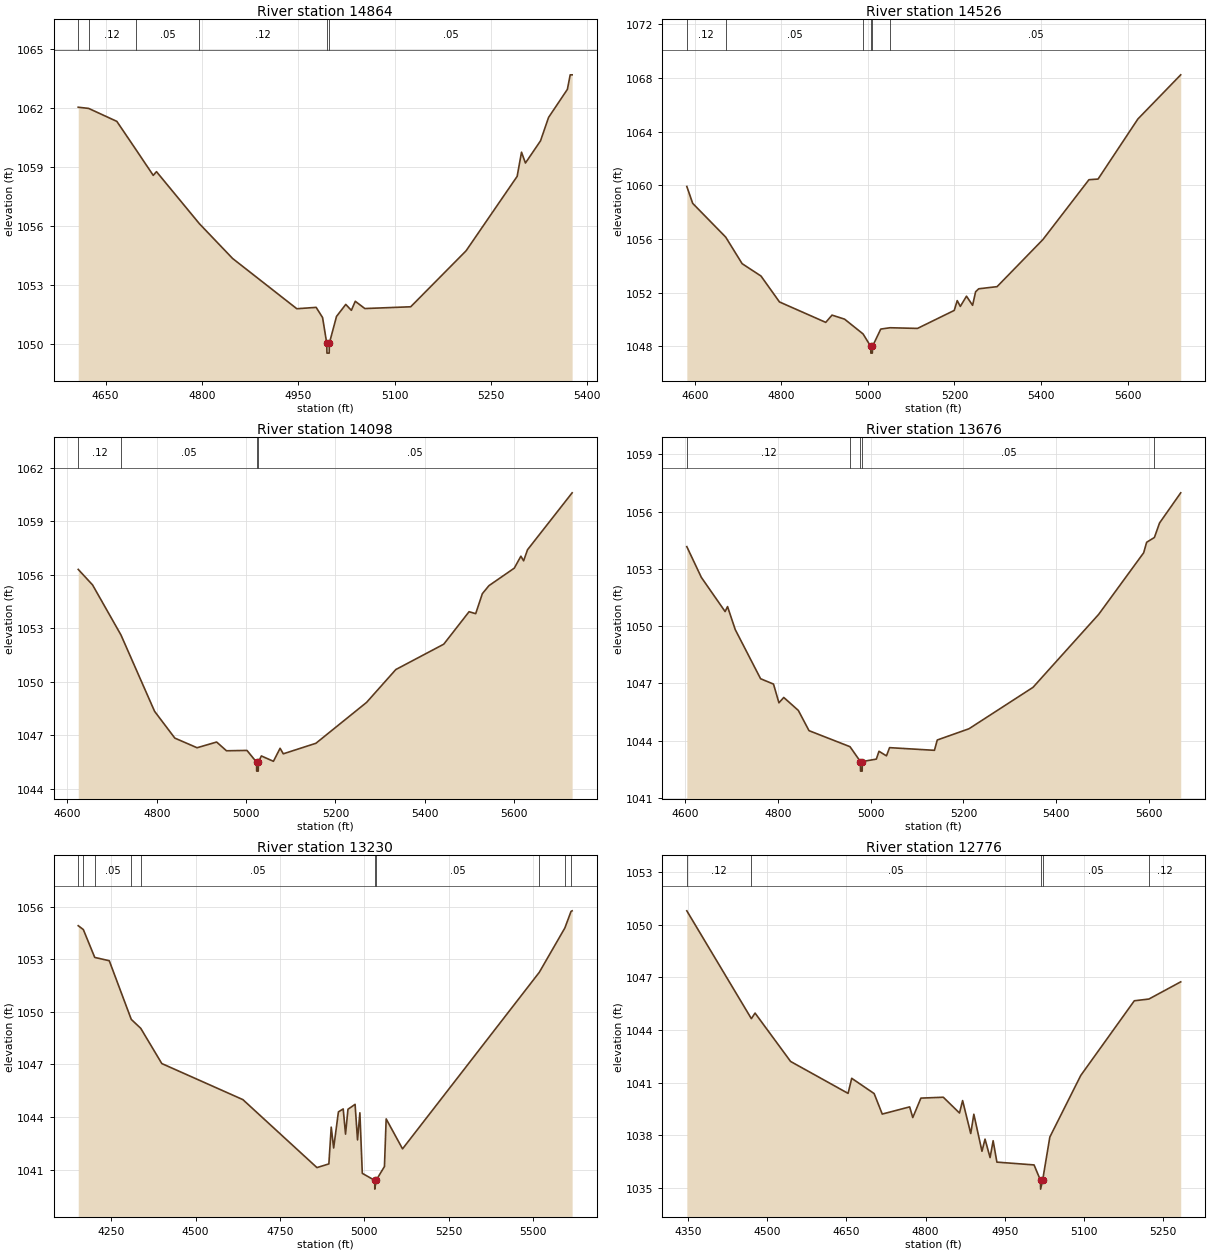
Type RM Length L Ch R = 1,14864,338,338,338
BEGIN DESCRIPTION:
MUD CREEK 31.0
END DESCRIPTION:
XS GIS Cut Line= 3
      2840255.68     10260053.15      2840272.25     10259661.00
      2840055.70     10259353.13
#Sta/Elev= 30
  4607.5 1062.05  4623.7 1061.99  4667.6 1061.33  4697.2 1059.90  4724.3 1058.58
  4729.3 1058.77  4796.1 1056.12  4847.8 1054.35  4947.8 1051.79  4977.9 1051.86
  4987.9 1051.34  4994.4 1050.03  4994.7 1049.53  4998.2 1049.53  4998.4 1050.03
  5009.6 1051.40  5024.0 1052.01  5032.7 1051.71  5038.8 1052.17  5053.7 1051.80
  5125.1 1051.89  5211.3 1054.74  5290.8 1058.53  5297.6 1059.76  5303.7 1059.21
  5327.2 1060.34  5339.7 1061.53  5369.0 1062.96  5373.4 1063.70  5376.4 1063.70
#Mann=6,-1,0
  4607.5    0.05       0  4623.7    0.12       0  4697.2    0.05       0
  4796.1    0.12       0  4994.4    0.05       0  4998.4    0.05       0
Bank Sta=4994.4,4998.4
Exp/Cntr=0.3,0.1

Type RM Length L Ch R = 1,14526,428,428,428
BEGIN DESCRIPTION:
MUD CREEK 30.0
END DESCRIPTION:
XS GIS Cut Line= 3
      2840355.68     10260003.11      2840610.00     10259671.00
      2840105.66     10259153.09
#Sta/Elev= 30
  4581.7 1059.91  4595.3 1058.65  4671.5 1056.14  4709.5 1054.16  4753.1 1053.24
  4795.8 1051.31  4902.7 1049.79  4917.2 1050.33  4946.2 1050.03  4988.9 1048.93
  5006.7 1048.00  5006.9 1047.50  5010.4 1047.50  5010.7 1048.00  5029.8 1049.29
  5051.3 1049.39  5114.7 1049.34  5199.6 1050.68  5206.5 1051.41  5213.7 1050.98
  5227.9 1051.74  5242.0 1051.06  5249.0 1052.07  5256.2 1052.29  5298.6 1052.45
  5404.6 1055.96  5510.8 1060.41  5531.9 1060.46  5623.9 1064.93  5722.9 1068.22
#Mann=6,-1,0
  4581.7    0.12       0  4671.5    0.05       0  4988.9    0.12       0
  5006.7    0.07       0  5010.7    0.12       0  5051.3    0.05       0
Bank Sta=5006.7,5010.7
Exp/Cntr=0.3,0.1

Type RM Length L Ch R = 1,14098,422,422,422
BEGIN DESCRIPTION:
MUD CREEK 29.0
END DESCRIPTION:
XS GIS Cut Line= 3
      2841355.70     10259653.12      2841004.00     10259521.00
      2840405.69     10259103.11
#Sta/Elev= 30
  4624.3 1056.30  4656.4 1055.43  4719.9 1052.63  4795.2 1048.35  4840.5 1046.85
  4890.3 1046.31  4934.1 1046.63  4956.1 1046.14  5002.0 1046.16  5023.5 1045.50
  5023.7 1045.00  5027.2 1045.00  5027.5 1045.50  5034.2 1045.85  5061.2 1045.55
  5076.1 1046.28  5083.3 1045.97  5156.3 1046.56  5269.7 1048.85  5335.1 1050.69
  5442.4 1052.11  5499.1 1053.93  5513.9 1053.82  5528.8 1054.94  5543.6 1055.39
  5600.3 1056.37  5615.1 1057.04  5621.2 1056.78  5629.9 1057.40  5729.8 1060.59
#Mann=4,-1,0
  4624.3    0.12       0  4719.9    0.05       0  5023.5    0.05       0
  5027.5    0.05       0
Bank Sta=5023.5,5027.5
Exp/Cntr=0.3,0.1

Type RM Length L Ch R = 1,13676,446,446,446
BEGIN DESCRIPTION:
MUD CREEK 28.0
END DESCRIPTION:
XS GIS Cut Line= 3
      2841355.67     10259553.08      2841241.50     10259174.00
      2840655.72     10258853.13
#Sta/Elev= 30
  4604.1 1054.16  4635.4 1052.55  4686.6 1050.76  4691.8 1051.02  4708.5 1049.81
  4763.0 1047.24  4790.8 1046.96  4802.5 1045.98  4812.9 1046.26  4844.3 1045.58
  4867.3 1044.52  4955.6 1043.68  4978.0 1042.90  4978.3 1042.40  4981.8 1042.40
  4982.0 1042.90  5012.3 1043.03  5018.0 1043.44  5034.1 1043.20  5040.8 1043.63
  5137.5 1043.49  5143.5 1044.03  5211.9 1044.62  5349.8 1046.79  5491.1 1050.61
  5588.1 1053.84  5594.5 1054.39  5611.2 1054.64  5622.3 1055.40  5667.9 1056.98
#Mann=5,-1,0
  4604.1    0.12       0  4955.6    0.05       0  4978.0    0.05       0
  4982.0    0.05       0  5611.2    0.12       0
Bank Sta=4978,4982
Exp/Cntr=0.3,0.1

Type RM Length L Ch R = 1,13230,454,454,454
BEGIN DESCRIPTION:
MUD CREEK 27.0
END DESCRIPTION:
XS GIS Cut Line= 3
      2841905.69     10259353.12      2841318.50     10258742.00
      2840705.64     10258803.12
#Sta/Elev= 30
  4152.5 1054.92  4167.6 1054.70  4201.4 1053.11  4244.5 1052.92  4309.7 1049.57
  4337.8 1049.06  4400.1 1047.05  4640.4 1044.99  4859.8 1041.11  4895.1 1041.32
  4902.1 1043.42  4909.3 1042.23  4923.4 1044.29  4937.6 1044.46  4944.5 1043.02
  4951.7 1044.44  4972.8 1044.72  4980.0 1042.69  4987.0 1044.24  4994.2 1040.78
  5031.0 1040.38  5031.2 1039.88  5035.0 1040.38  5059.8 1041.17  5064.9 1043.89
  5113.4 1042.18  5518.6 1052.26  5594.3 1054.79  5612.7 1055.74  5615.9 1055.77
#Mann=10,-1,0
  4152.5    0.05       0  4167.6    0.12       0  4201.4    0.05       0
  4309.7    0.12       0  4337.8    0.05       0  5031.0    0.05       0
  5035.0    0.05       0  5518.6    0.12       0  5594.3    0.05       0
  5612.7    0.12       0
Bank Sta=5031,5035
Exp/Cntr=0.3,0.1

Type RM Length L Ch R = 1,12776,425,425,425
BEGIN DESCRIPTION:
MUD CREEK 26.0
END DESCRIPTION:
XS GIS Cut Line= 3
      2841955.71     10259053.15      2841612.25     10258498.00
      2841755.68     10258253.11
#Sta/Elev= 30
  4347.2 1050.80  4469.6 1044.65  4476.6 1044.97  4544.0 1042.21  4653.0 1040.39
  4659.9 1041.25  4702.4 1040.38  4717.8 1039.21  4769.8 1039.62  4775.7 1039.01
  4791.1 1040.12  4833.6 1040.17  4864.3 1039.27  4870.2 1039.98  4885.6 1038.10
  4891.5 1039.20  4906.9 1037.09  4912.7 1037.78  4922.3 1036.73  4928.1 1037.69
  4935.2 1036.47  5005.7 1036.31  5017.9 1035.43  5018.1 1034.93  5021.9 1035.43
  5035.6 1037.90  5094.2 1041.41  5195.8 1045.67  5223.5 1045.77  5283.8 1046.75
#Mann=5,-1,0
  4347.2    0.12       0  4469.6    0.05       0  5017.9    0.03       0
  5021.9    0.05       0  5223.5    0.12       0
Bank Sta=5017.9,5021.9
Exp/Cntr=0.3,0.1

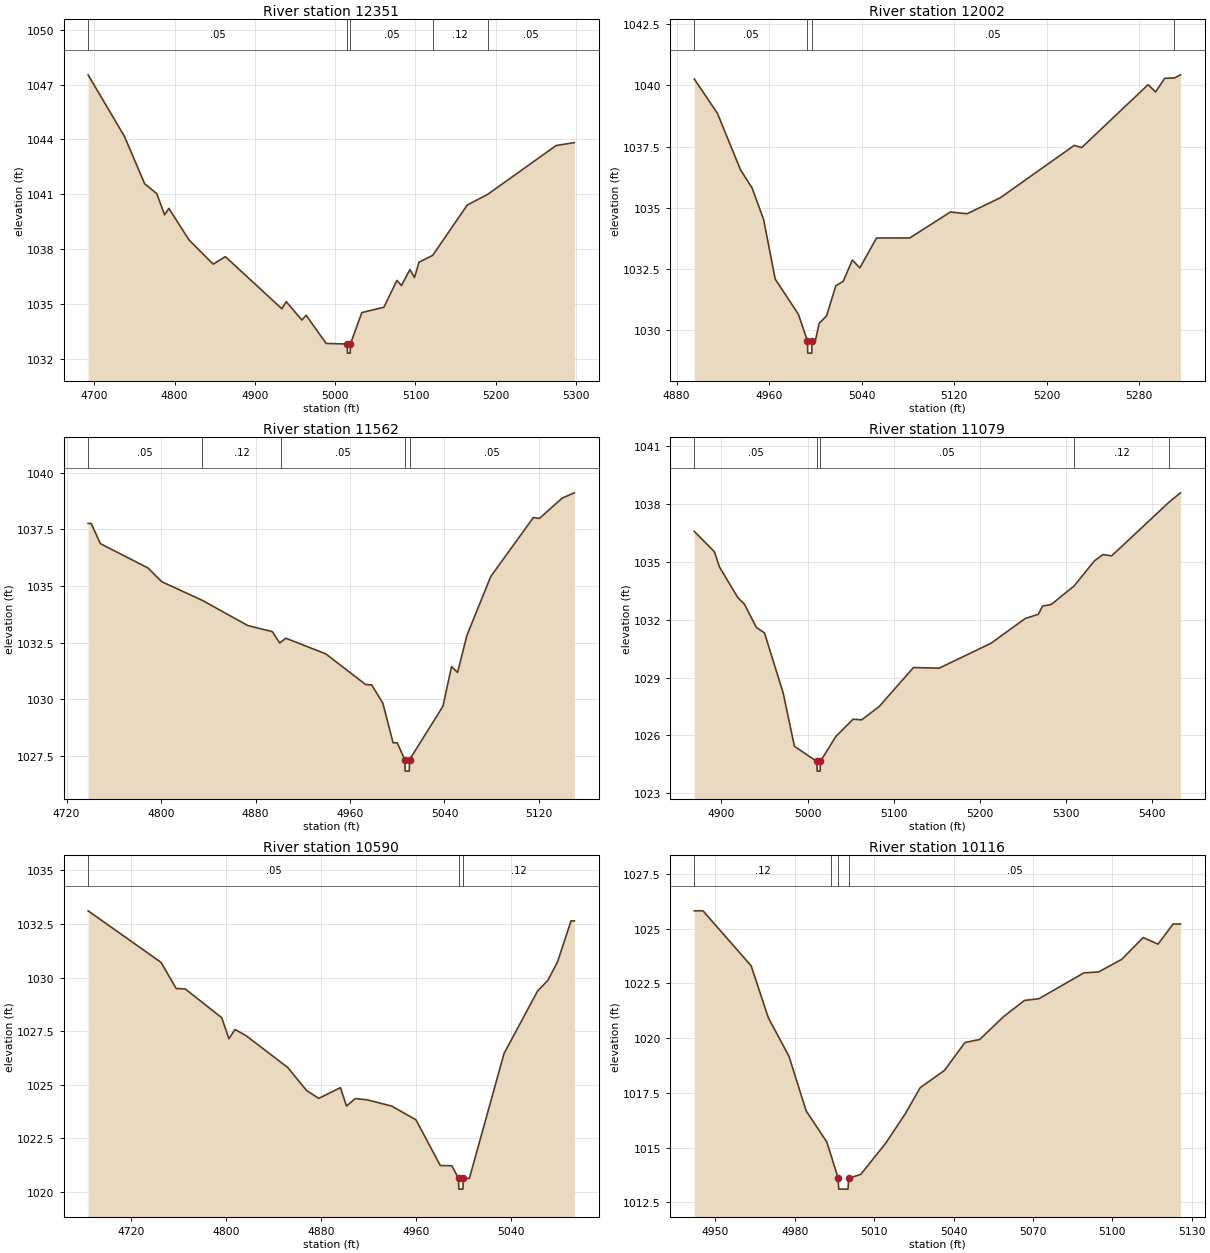
Type RM Length L Ch R = 1,12351,349,349,349
BEGIN DESCRIPTION:
MUD CREEK 25.0
END DESCRIPTION:
XS GIS Cut Line= 3
      2842105.70     10258953.14      2841997.75     10258665.00
      2841855.70     10258403.15
#Sta/Elev= 30
  4692.3 1047.53  4737.7 1044.15  4762.7 1041.57  4777.8 1041.03  4787.6 1039.87
  4792.9 1040.22  4817.9 1038.50  4848.1 1037.17  4863.2 1037.58  4933.6 1034.73
  4939.0 1035.12  4958.5 1034.11  4963.9 1034.37  4988.8 1032.83  5015.0 1032.80
  5015.3 1032.30  5018.8 1032.30  5019.0 1032.80  5033.2 1034.52  5060.7 1034.81
  5076.9 1036.28  5082.6 1036.00  5093.1 1036.87  5098.8 1036.44  5104.5 1037.28
  5121.5 1037.65  5164.4 1040.40  5190.0 1040.99  5275.2 1043.66  5297.9 1043.82
#Mann=5,-1,0
  4692.3    0.05       0  5015.0    0.03       0  5019.0    0.05       0
  5121.5    0.12       0  5190.0    0.05       0
Bank Sta=5015,5019
Exp/Cntr=0.3,0.1

Type RM Length L Ch R = 1,12002,440,440,440
BEGIN DESCRIPTION:
MUD CREEK 24.0
END DESCRIPTION:
XS GIS Cut Line= 3
      2842355.69     10258603.11      2842251.00     10258602.00
      2842005.69     10258403.12
#Sta/Elev= 30
  4895.3 1040.26  4915.3 1038.86  4935.3 1036.55  4945.3 1035.81  4955.3 1034.52
  4965.3 1032.09  4985.3 1030.66  4993.2 1029.57  4993.4 1029.07  4996.9 1029.07
  4997.2 1029.57  5000.0 1029.57  5003.3 1030.29  5009.7 1030.59  5017.7 1031.82
  5024.1 1032.00  5032.0 1032.87  5038.5 1032.55  5052.9 1033.77  5081.6 1033.77
  5116.8 1034.83  5131.2 1034.76  5159.9 1035.41  5223.9 1037.55  5230.3 1037.46
  5287.8 1040.03  5294.2 1039.73  5302.2 1040.29  5310.4 1040.30  5315.8 1040.43
#Mann=4,-1,0
  4895.3    0.05       0  4993.2    0.03       0  4997.2    0.05       0
  5310.4    0.12       0
Bank Sta=4993.2,4997.2
Exp/Cntr=0.3,0.1

Type RM Length L Ch R = 1,11562,483,483,483
BEGIN DESCRIPTION:
MUD CREEK 23.0
END DESCRIPTION:
XS GIS Cut Line= 3
      2842505.67     10258253.11      2842254.00     10258181.00
      2842105.64     10258203.12
#Sta/Elev= 30
  4738.2 1037.76  4740.8 1037.76  4748.6 1036.87  4788.8 1035.80  4800.6 1035.19
  4834.9 1034.37  4873.4 1033.26  4894.2 1032.99  4900.5 1032.49  4901.9 1032.55
  4905.7 1032.70  4939.5 1032.01  4973.2 1030.66  4978.4 1030.64  4987.8 1029.84
  4996.5 1028.09  5000.0 1028.09  5006.4 1027.34  5006.7 1026.84  5010.2 1026.84
  5010.4 1027.34  5038.7 1029.70  5046.0 1031.45  5051.1 1031.19  5059.0 1032.82
  5079.2 1035.42  5115.3 1038.02  5120.4 1037.98  5139.8 1038.88  5150.0 1039.11
#Mann=5,-1,0
  4738.2    0.05       0  4834.9    0.12       0  4901.9    0.05       0
  5006.4    0.03       0  5010.4    0.05       0
Bank Sta=5006.4,5010.4
Exp/Cntr=0.3,0.1

Type RM Length L Ch R = 1,11079,489,489,489
BEGIN DESCRIPTION:
MUD CREEK 22.0
END DESCRIPTION:
XS GIS Cut Line= 3
      2842605.70     10258003.15      2842538.50     10257890.00
      2842105.70     10257903.11
#Sta/Elev= 30
  4868.4 1036.58  4891.7 1035.53  4897.7 1034.73  4919.1 1033.14  4926.6 1032.81
  4940.5 1031.60  4949.9 1031.32  4971.7 1028.19  4984.7 1025.44  5010.8 1024.65
  5011.1 1024.15  5014.6 1024.15  5014.8 1024.65  5032.8 1025.95  5052.8 1026.84
  5062.8 1026.81  5082.9 1027.49  5122.9 1029.52  5152.9 1029.49  5212.9 1030.78
  5252.9 1032.07  5267.9 1032.28  5272.9 1032.71  5282.9 1032.79  5309.4 1033.75
  5333.0 1035.05  5343.0 1035.38  5353.0 1035.31  5420.0 1038.11  5433.0 1038.58
#Mann=5,-1,0
  4868.4    0.05       0  5010.8    0.03       0  5014.8    0.05       0
  5309.4    0.12       0  5420.0    0.05       0
Bank Sta=5010.8,5014.8
Exp/Cntr=0.3,0.1

Type RM Length L Ch R = 1,10590,474,474,474
BEGIN DESCRIPTION:
MUD CREEK 21.0
END DESCRIPTION:
XS GIS Cut Line= 3
      2842705.68     10257903.12      2842771.75     10257594.00
      2842855.72     10257553.10
#Sta/Elev= 30
  4683.9 1033.11  4745.3 1030.71  4758.1 1029.49  4765.7 1029.47  4796.4 1028.13
  4802.5 1027.15  4807.6 1027.58  4816.8 1027.30  4852.0 1025.81  4868.0 1024.73
  4878.2 1024.37  4896.4 1024.87  4901.5 1024.01  4908.9 1024.36  4919.1 1024.30
  4939.6 1024.01  4960.0 1023.37  4980.5 1021.24  4990.2 1021.23  4995.9 1020.64
  4996.1 1020.14  4999.6 1020.14  4999.9 1020.64  5005.0 1020.64  5034.2 1026.46
  5062.3 1029.36  5071.1 1029.87  5079.3 1030.74  5090.6 1032.64  5093.4 1032.64
#Mann=3,-1,0
  4683.9    0.05       0  4995.9    0.07       0  4999.9    0.12       0
Bank Sta=4995.9,4999.9
Exp/Cntr=0.3,0.1

Type RM Length L Ch R = 1,10116,945,945,945
BEGIN DESCRIPTION:
MUD CREEK 20.0
END DESCRIPTION:
XS GIS Cut Line= 3
      2843055.68     10257953.12      2843100.25     10257916.00
      2843155.70     10257803.08
#Sta/Elev= 29
  4942.0 1025.81  4945.3 1025.81  4963.5 1023.30  4970.0 1020.93  4977.8 1019.17
  4984.3 1016.68  4992.1 1015.26  4993.8 1014.61  4996.4 1013.61  4996.6 1013.11
  5000.1 1013.11  5000.4 1013.61  5004.9 1013.78  5014.4 1015.21  5021.8 1016.56
  5027.4 1017.74  5036.6 1018.53  5044.3 1019.80  5049.9 1019.94  5058.9 1020.98
  5066.8 1021.72  5072.3 1021.80  5089.3 1022.98  5094.8 1023.02  5103.5 1023.59
  5111.7 1024.59  5117.3 1024.29  5123.0 1025.21  5125.8 1025.21
#Mann=4,-1,0
  4942.0    0.12       0  4993.8    0.05       0  4996.4    0.03       0
  5000.4    0.05       0
Bank Sta=4996.4,5000.4
Exp/Cntr=0.3,0.1

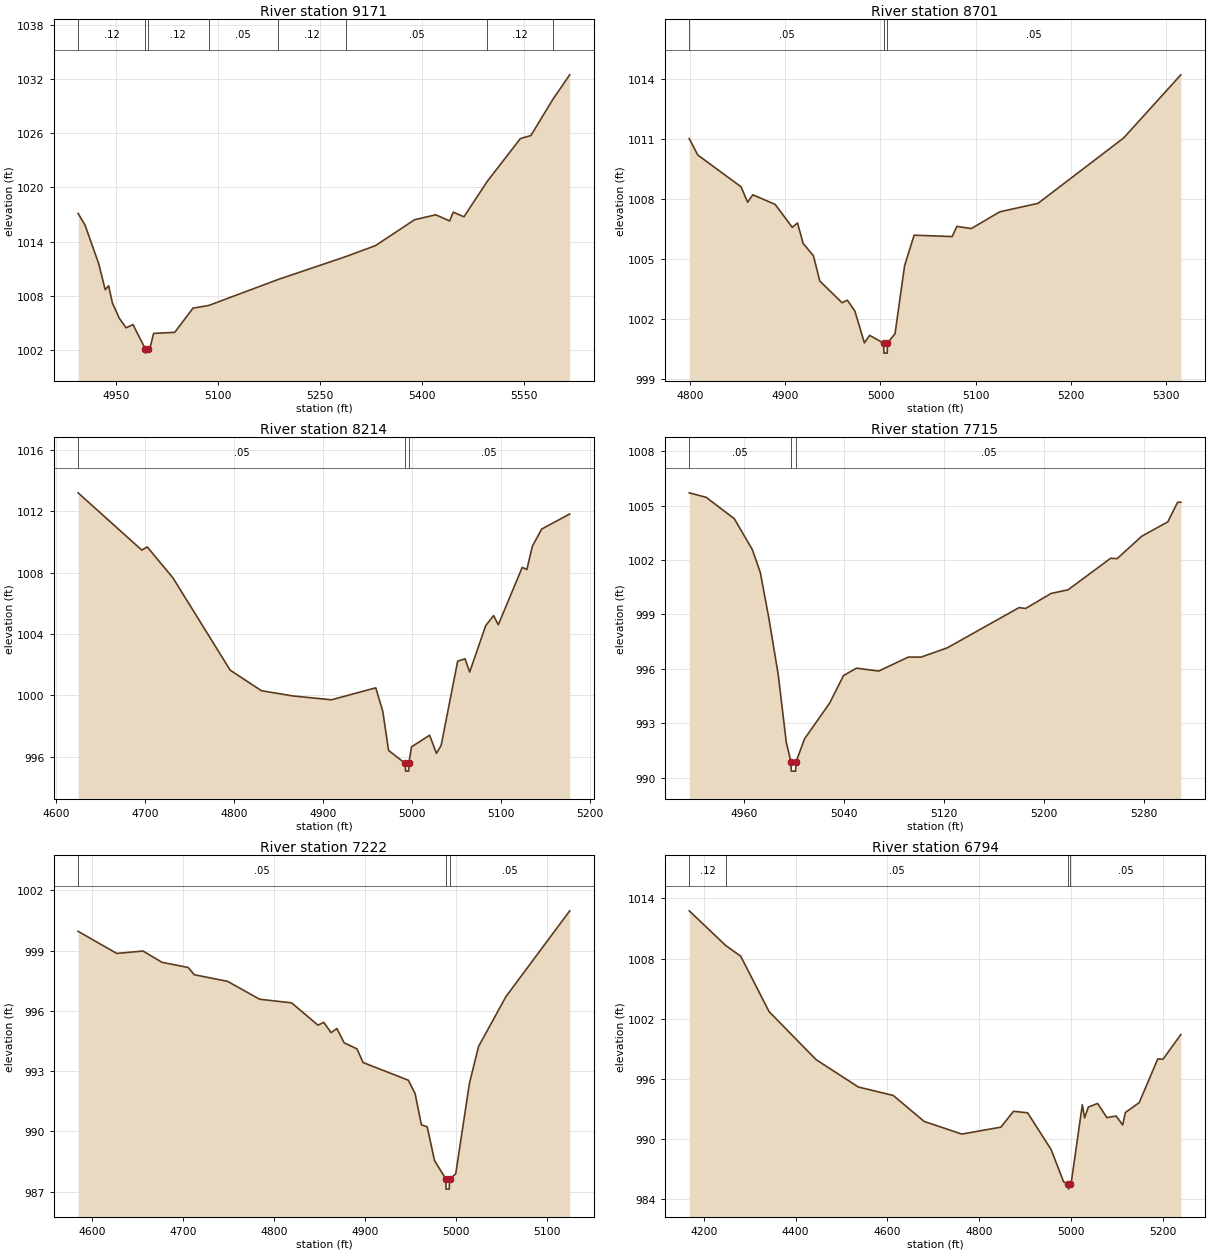
Type RM Length L Ch R = 1,9171,470,470,470
BEGIN DESCRIPTION:
MUD CREEK 19.0
END DESCRIPTION:
XS GIS Cut Line= 3
      2843905.73     10257753.11      2843801.00     10257765.00
      2843205.72     10257603.12
#Sta/Elev= 30
  4894.6 1017.11  4904.7 1015.83  4924.8 1011.57  4934.4 1008.67  4939.4 1009.11
  4945.0 1007.21  4955.0 1005.53  4965.1 1004.46  4975.2 1004.82  4993.1 1002.16
  4993.4 1001.66  4997.1 1002.16  5000.0 1002.16  5005.5 1003.84  5036.6 1003.96
  5063.4 1006.64  5086.5 1006.93  5187.6 1009.78  5288.8 1012.36  5331.5 1013.55
  5388.9 1016.41  5420.0 1016.96  5440.5 1016.28  5445.7 1017.25  5461.5 1016.74
  5495.5 1020.63  5544.4 1025.39  5559.9 1025.73  5592.3 1029.75  5616.9 1032.44
#Mann=8,-1,0
  4894.6    0.12       0  4993.1    0.07       0  4997.1    0.12       0
  5086.5    0.05       0  5187.6    0.12       0  5288.8    0.05       0
  5495.5    0.12       0  5592.3    0.05       0
Bank Sta=4993.1,4997.1
Exp/Cntr=0.3,0.1

Type RM Length L Ch R = 1,8701,487,487,487
BEGIN DESCRIPTION:
MUD CREEK 18.0
END DESCRIPTION:
XS GIS Cut Line= 3
      2843955.66     10257253.12      2843771.00     10257333.00
      2843455.64     10257353.11
#Sta/Elev= 30
  4798.8 1011.00  4807.8 1010.18  4853.3 1008.59  4860.2 1007.82  4865.7 1008.19
  4889.2 1007.71  4907.2 1006.56  4912.7 1006.78  4918.6 1005.76  4929.5 1005.14
  4936.1 1003.88  4959.6 1002.79  4965.1 1002.92  4973.1 1002.37  4983.1 1000.78
  4988.6 1001.16  5003.3 1000.77  5003.6 1000.27  5007.1 1000.27  5007.3 1000.77
  5015.3 1001.24  5025.4 1004.65  5035.4 1006.17  5075.4 1006.10  5080.4 1006.61
  5095.5 1006.50  5125.6 1007.34  5165.7 1007.76  5255.8 1011.03  5316.0 1014.19
#Mann=3,-1,0
  4798.8    0.05       0  5003.3    0.03       0  5007.3    0.05       0
Bank Sta=5003.3,5007.3
Exp/Cntr=0.3,0.1

Type RM Length L Ch R = 1,8214,499,499,499
BEGIN DESCRIPTION:
MUD CREEK 17.0
END DESCRIPTION:
XS GIS Cut Line= 3
      2843955.70     10257103.12      2843659.75     10256872.00
      2843605.69     10256703.14
#Sta/Elev= 30
  4624.5 1013.21  4696.0 1009.48  4702.3 1009.68  4731.2 1007.66  4795.5 1001.65
  4830.7 1000.31  4866.0  999.97  4909.4  999.72  4959.2 1000.50  4967.1  998.97
  4973.6  996.42  4992.4  995.57  4992.7  995.07  4996.2  995.07  4996.4  995.57
  4999.4  996.65  5019.8  997.41  5027.4  996.23  5032.7  996.74  5051.3 1002.24
  5059.6 1002.39  5064.8 1001.53  5082.8 1004.55  5091.7 1005.21  5097.0 1004.61
  5123.9 1008.35  5129.1 1008.21  5135.3 1009.73  5145.8 1010.85  5177.3 1011.83
#Mann=3,-1,0
  4624.5    0.05       0  4992.4    0.05       0  4996.4    0.05       0
Bank Sta=4992.4,4996.4
Exp/Cntr=0.3,0.1

Type RM Length L Ch R = 1,7715,493,493,493
BEGIN DESCRIPTION:
MUD CREEK 16.0
END DESCRIPTION:
XS GIS Cut Line= 3
      2844105.67     10256703.09      2844053.50     10256637.00
      2843755.69     10256553.11
#Sta/Elev= 30
  4915.8 1005.71  4929.4 1005.46  4951.9 1004.28  4966.3 1002.58  4972.7 1001.32
  4979.5  998.82  4987.1  995.66  4993.5  991.95  4997.3  990.86  4997.5  990.36
  5001.0  990.36  5001.3  990.86  5008.1  992.14  5028.2  994.11  5039.3  995.63
  5049.7  996.04  5067.5  995.88  5091.2  996.65  5101.5  996.65  5122.4  997.16
  5179.9  999.38  5185.1  999.33  5205.5 1000.16  5219.1 1000.36  5253.2 1002.10
  5258.4 1002.08  5278.2 1003.32  5299.0 1004.11  5306.8 1005.19  5309.4 1005.19
#Mann=3,-1,0
  4915.8    0.05       0  4997.3    0.03       0  5001.3    0.05       0
Bank Sta=4997.3,5001.3
Exp/Cntr=0.3,0.1

Type RM Length L Ch R = 1,7222,428,428,428
BEGIN DESCRIPTION:
MUD CREEK 15.0
END DESCRIPTION:
XS GIS Cut Line= 3
      2844305.70     10256453.13      2843980.75     10256195.00
      2843855.71     10256203.11
#Sta/Elev= 30
  4585.0  999.96  4627.5  998.86  4656.3  998.98  4677.1  998.42  4706.0  998.16
  4712.7  997.80  4749.3  997.47  4784.5  996.58  4819.7  996.40  4848.6  995.29
  4855.0  995.43  4863.0  994.92  4869.4  995.12  4877.4  994.41  4891.5  994.11
  4898.2  993.43  4947.9  992.55  4955.4  991.88  4962.3  990.33  4968.7  990.23
  4976.7  988.55  4989.2  987.63  4989.4  987.13  4992.9  987.13  4993.2  987.63
  5000.0  987.89  5015.1  992.40  5025.1  994.23  5055.2  996.71  5125.3 1000.98
#Mann=3,-1,0
  4585.0    0.05       0  4989.2    0.05       0  4993.2    0.05       0
Bank Sta=4989.2,4993.2
Exp/Cntr=0.3,0.1

Type RM Length L Ch R = 1,6794,493,493,493
BEGIN DESCRIPTION:
MUD CREEK 14.0
END DESCRIPTION:
XS GIS Cut Line= 3
      2844855.66     10256003.11      2844043.25     10255825.00
      2843805.71     10255853.11
#Sta/Elev= 30
  4168.3 1012.77  4247.8 1009.31  4280.4 1008.25  4342.3 1002.72  4444.7  997.93
  4536.8  995.20  4612.7  994.36  4680.1  991.77  4762.0  990.51  4847.2  991.20
  4874.7  992.78  4905.4  992.63  4956.6  988.97  4983.8  985.75  4994.1  985.52
  4994.4  985.02  4998.2  985.52  5000.0  985.52  5024.6  993.43  5029.6  992.13
  5037.8  993.21  5058.0  993.56  5078.1  992.15  5098.2  992.31  5112.5  991.42
  5118.4  992.66  5148.6  993.65  5188.9  998.00  5200.3  997.97  5239.2 1000.43
#Mann=4,-1,0
  4168.3    0.12       0  4247.8    0.05       0  4994.1    0.05       0
  4998.2    0.05       0
Bank Sta=4994.1,4998.2
Exp/Cntr=0.3,0.1

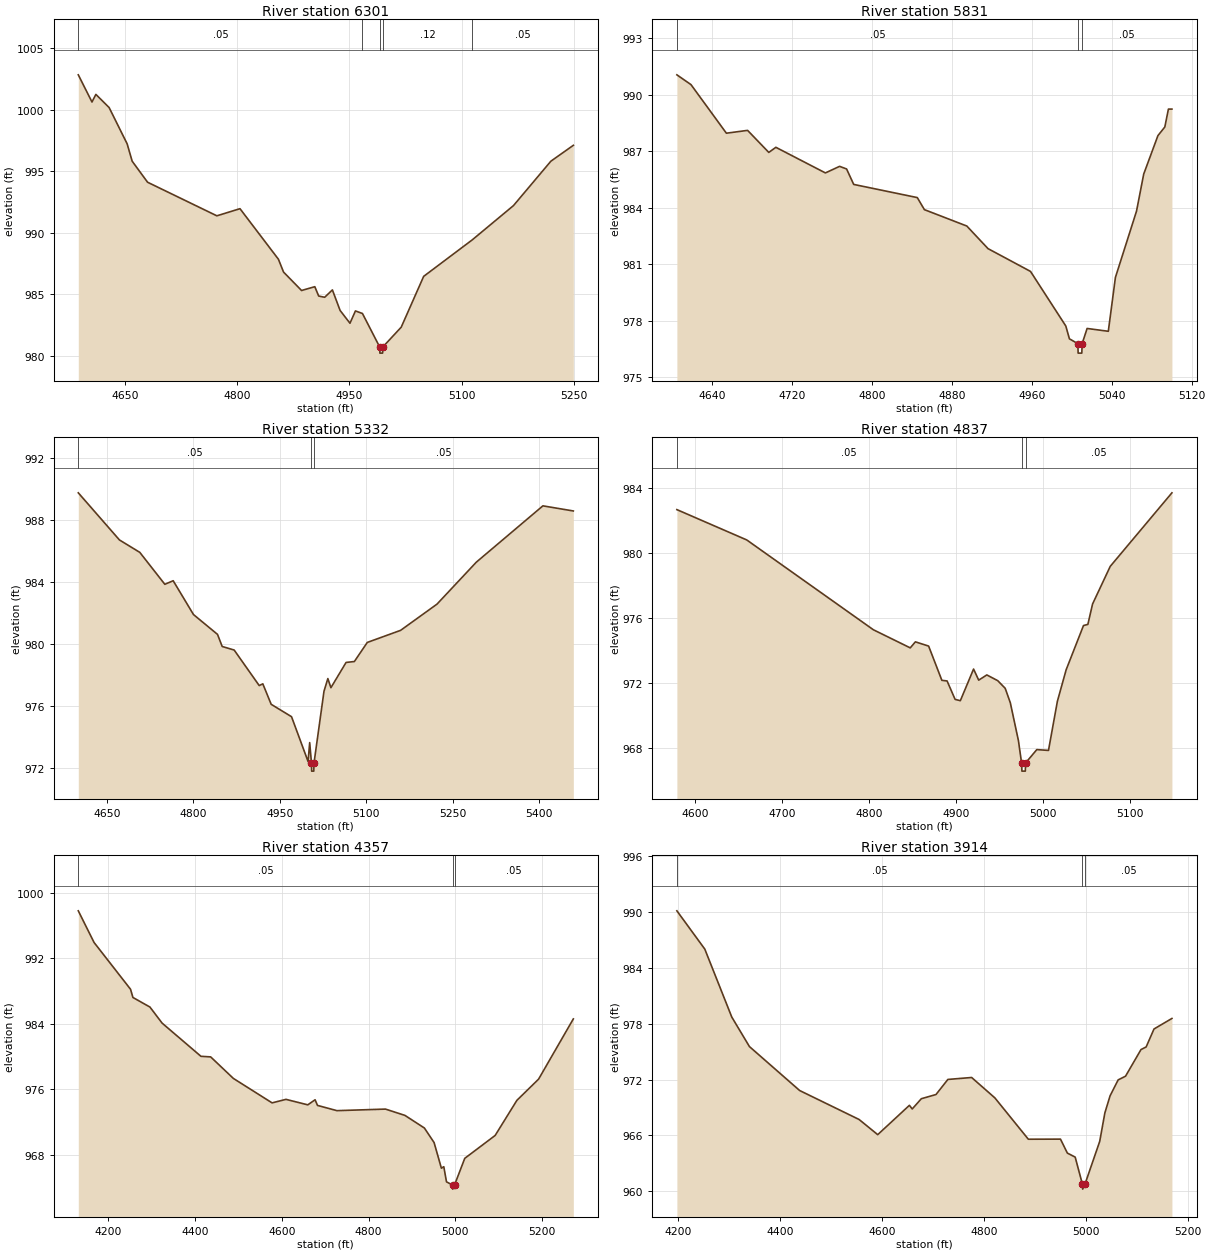
Type RM Length L Ch R = 1,6301,470,470,470
BEGIN DESCRIPTION:
MUD CREEK 13.0
END DESCRIPTION:
XS GIS Cut Line= 3
      2844755.70     10255553.12      2844355.00     10255456.00
      2844105.72     10255453.11
#Sta/Elev= 30
  4587.7 1002.82  4606.0 1000.61  4611.2 1001.23  4628.9 1000.16  4653.0  997.21
  4659.7  995.80  4680.3  994.09  4772.9  991.36  4803.8  991.94  4855.2  987.83
  4862.0  986.79  4886.1  985.29  4903.8  985.60  4909.0  984.84  4917.0  984.74
  4927.3  985.34  4937.6  983.67  4950.8  982.63  4958.1  983.63  4967.5  983.42
  4990.5  980.70  4990.8  980.20  4994.4  980.20  4994.7  980.70  5019.3  982.31
  5049.3  986.44  5114.1  989.40  5169.3  992.19  5219.3  995.80  5249.3  997.09
#Mann=5,-1,0
  4587.7    0.05       0  4967.5    0.12       0  4990.5    0.07       0
  4994.7    0.12       0  5114.1    0.05       0
Bank Sta=4990.5,4994.7
Exp/Cntr=0.3,0.1

Type RM Length L Ch R = 1,5831,499,499,499
BEGIN DESCRIPTION:
MUD CREEK 12.0
END DESCRIPTION:
XS GIS Cut Line= 3
      2844755.70     10255303.13      2844477.50     10255023.00
      2844405.69     10254953.12
#Sta/Elev= 30
  4605.2  991.05  4619.3  990.53  4654.7  987.95  4675.9  988.10  4697.1  986.93
  4704.2  987.20  4753.7  985.84  4767.9  986.19  4774.9  986.05  4782.0  985.23
  4845.6  984.53  4852.7  983.89  4895.1  983.02  4916.3  981.82  4958.8  980.61
  4994.1  977.71  4997.7  977.03  5006.2  976.77  5006.4  976.27  5010.1  976.27
  5010.4  976.77  5015.4  977.58  5036.6  977.43  5043.7  980.29  5064.8  983.81
  5072.0  985.78  5086.2  987.82  5093.1  988.28  5096.7  989.23  5100.2  989.23
#Mann=3,-1,0
  4605.2    0.05       0  5006.2    0.05       0  5010.4    0.05       0
Bank Sta=5006.2,5010.4
Exp/Cntr=0.3,0.1

Type RM Length L Ch R = 1,5332,495,495,495
BEGIN DESCRIPTION:
MUD CREEK 11.0
END DESCRIPTION:
XS GIS Cut Line= 3
      2845055.69     10254853.11      2844741.00     10254607.00
      2844305.67     10254753.12
#Sta/Elev= 30
  4600.5  989.77  4671.9  986.73  4707.2  985.93  4750.6  983.87  4765.1  984.10
  4800.3  981.92  4842.0  980.64  4850.1  979.86  4870.9  979.63  4914.3  977.34
  4920.6  977.45  4935.1  976.13  4970.4  975.33  4999.1  972.44  5001.9  973.66
  5005.0  972.32  5005.3  971.82  5009.0  971.82  5009.3  972.32  5026.7  976.97
  5033.4  977.79  5038.7  977.20  5065.0  978.83  5079.4  978.89  5101.8  980.12
  5159.6  980.90  5222.7  982.59  5291.0  985.30  5406.4  988.93  5459.2  988.60
#Mann=3,-1,0
  4600.5    0.05       0  5005.0    0.05       0  5009.3    0.05       0
Bank Sta=5005,5009.3
Exp/Cntr=0.3,0.1

Type RM Length L Ch R = 1,4837,480,480,480
BEGIN DESCRIPTION:
MUD CREEK 10.0
END DESCRIPTION:
XS GIS Cut Line= 3
      2845155.66     10254403.09      2844801.75     10254176.00
      2844655.73     10254153.12
#Sta/Elev= 30
  4579.5  982.65  4659.7  980.79  4805.1  975.28  4847.4  974.17  4853.3  974.54
  4868.5  974.28  4883.7  972.18  4889.7  972.14  4898.9  971.01  4904.9  970.93
  4920.1  972.87  4926.0  972.19  4935.3  972.51  4947.8  972.16  4956.4  971.69
  4962.3  970.80  4971.6  968.48  4975.2  967.11  4975.6  966.61  4979.5  966.61
  4979.8  967.11  4992.7  967.93  5006.1  967.88  5016.3  970.89  5026.4  972.83
  5046.3  975.54  5051.3  975.61  5056.7  976.86  5077.0  979.17  5147.8  983.68
#Mann=3,-1,0
  4579.5    0.05       0  4975.2    0.05       0  4979.8    0.05       0
Bank Sta=4975.2,4979.8
Exp/Cntr=0.3,0.1

Type RM Length L Ch R = 1,4357,443,443,443
BEGIN DESCRIPTION:
MUD CREEK 9.0
END DESCRIPTION:
XS GIS Cut Line= 3
      2845655.73     10254103.13      2844877.50     10253716.00
      2844605.71     10253703.11
#Sta/Elev= 30
  4130.8  997.78  4167.2  993.91  4251.2  988.20  4256.8  987.19  4296.0  986.02
  4324.0  984.06  4413.6  980.00  4436.0  979.93  4488.3  977.30  4577.6  974.31
  4609.6  974.74  4659.9  974.07  4676.7  974.69  4682.3  974.00  4727.1  973.36
  4839.1  973.55  4883.9  972.78  4928.7  971.24  4951.1  969.46  4967.9  966.33
  4973.5  966.51  4979.7  964.66  4993.6  964.27  4993.9  963.77  4998.2  964.27
  5021.8  967.53  5091.9  970.33  5142.0  974.62  5192.0  977.21  5272.1  984.57
#Mann=3,-1,0
  4130.8    0.05       0  4993.6    0.03       0  4998.2    0.05       0
Bank Sta=4993.6,4998.2
Exp/Cntr=0.3,0.1

Type RM Length L Ch R = 1,3914,465,465,465
BEGIN DESCRIPTION:
MUD CREEK 8.0
END DESCRIPTION:
XS GIS Cut Line= 3
      2845655.72     10253603.13      2844922.25     10253279.00
      2844755.69     10253303.11
#Sta/Elev= 30
  4198.1  990.13  4252.8  986.02  4305.7  978.72  4340.3  975.55  4438.7  970.83
  4555.2  967.72  4591.7  966.09  4653.8  969.24  4659.3  968.85  4677.2  969.95
  4705.9  970.40  4729.2  972.02  4775.8  972.23  4821.3  970.04  4886.9  965.60
  4949.9  965.61  4963.4  964.11  4978.7  963.68  4993.0  960.74  4993.4  960.24
  4997.7  960.74  5026.8  965.37  5036.9  968.43  5047.1  970.26  5062.9  971.97
  5077.4  972.37  5107.7  975.23  5117.8  975.51  5133.2  977.44  5168.3  978.57
#Mann=3,-1,0
  4198.1    0.05       0  4993.0    0.03       0  4997.7    0.05       0
Bank Sta=4993,4997.7
Exp/Cntr=0.3,0.1

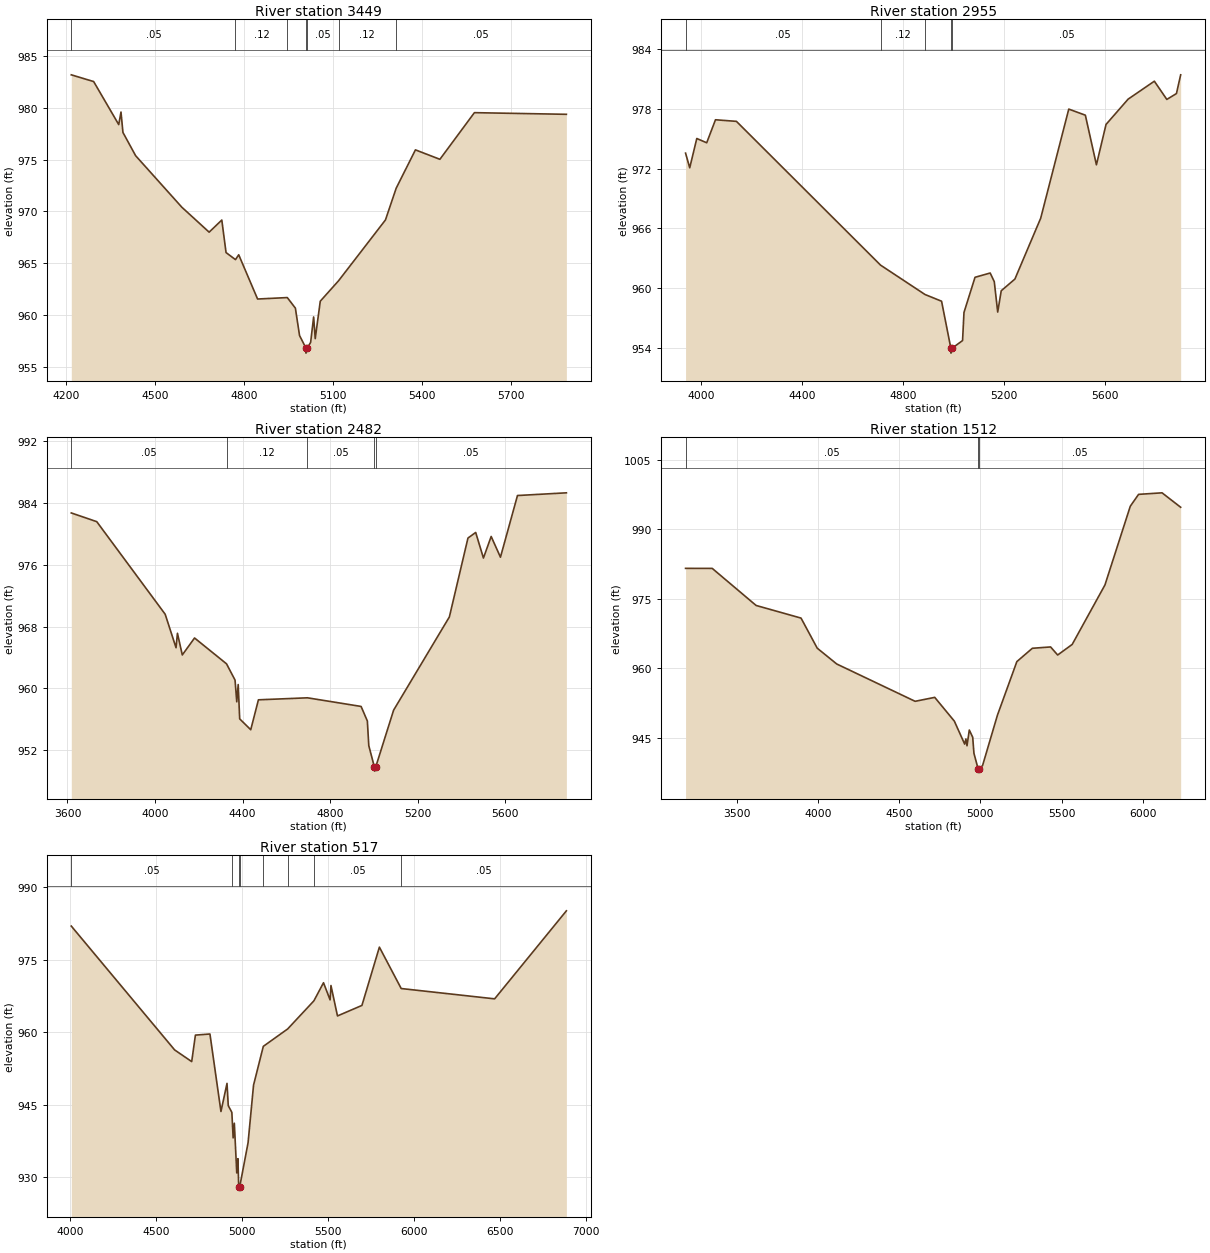
Type RM Length L Ch R = 1,3449,494,494,494
BEGIN DESCRIPTION:
MUD CREEK 7.0
END DESCRIPTION:
XS GIS Cut Line= 3
      2845742.51     10253522.33      2845228.50     10252933.00
      2844409.25     10253272.22
#Sta/Elev= 30
  4218.0  983.17  4293.4  982.52  4377.9  978.37  4385.5  979.58  4392.1  977.61
  4434.8  975.37  4590.5  970.40  4682.6  967.99  4725.3  969.16  4739.6  966.02
  4771.4  965.34  4782.3  965.81  4845.9  961.54  4946.0  961.68  4973.3  960.66
  4987.3  958.02  5008.6  956.82  5008.9  956.32  5013.3  956.82  5024.7  957.35
  5034.8  959.81  5040.2  957.72  5057.2  961.33  5118.8  963.30  5276.9  969.17
  5312.9  972.22  5377.9  975.93  5460.4  975.02  5576.7  979.52  5886.7  979.36
#Mann=7,-1,0
  4218.0    0.05       0  4771.4    0.12       0  4946.0    0.05       0
  5008.6    0.05       0  5013.3    0.05       0  5118.8    0.12       0
  5312.9    0.05       0
Bank Sta=5008.6,5013.3
Exp/Cntr=0.3,0.1

Type RM Length L Ch R = 1,2955,473,473,473
BEGIN DESCRIPTION:
MUD CREEK 6.0
END DESCRIPTION:
XS GIS Cut Line= 3
      2845869.74     10253509.43      2845399.25     10252558.00
      2844972.14     10251764.55
#Sta/Elev= 30
  3938.6  973.56  3955.1  972.09  3983.1  975.03  4022.4  974.60  4057.2  976.91
  4140.2  976.75  4711.6  962.32  4887.9  959.37  4953.4  958.70  4990.1  953.99
  4990.5  953.49  4995.4  953.99  5036.6  954.75  5042.2  957.57  5086.0  961.10
  5146.1  961.53  5162.3  960.66  5175.9  957.61  5189.9  959.75  5244.0  960.92
  5346.3  967.03  5457.6  977.98  5523.3  977.37  5567.2  972.39  5605.3  976.44
  5692.9  978.98  5796.8  980.78  5846.3  978.95  5884.4  979.54  5901.1  981.42
#Mann=5,-1,0
  3938.6    0.05       0  4711.6    0.12       0  4887.9    0.05       0
  4990.1    0.05       0  4995.4    0.05       0
Bank Sta=4990.1,4995.4
Exp/Cntr=0.3,0.1

Type RM Length L Ch R = 1,2482,970,970,970
BEGIN DESCRIPTION:
MUD CREEK 5.0
END DESCRIPTION:
XS GIS Cut Line= 3
      2846827.58     10253294.47      2845763.50     10252412.00
      2845135.43     10251797.62
#Sta/Elev= 30
  3617.6  982.73  3733.9  981.60  4046.4  969.59  4095.9  965.25  4102.4  967.12
  4124.5  964.31  4180.5  966.51  4326.5  963.16  4365.4  961.05  4373.3  958.23
  4379.8  960.47  4386.6  956.02  4437.1  954.61  4472.2  958.49  4696.2  958.75
  4941.1  957.63  4969.7  955.74  4976.2  952.55  5002.1  949.74  5002.5  949.24
  5007.4  949.74  5089.6  957.15  5344.2  969.24  5429.1  979.47  5464.4  980.20
  5499.8  976.88  5535.1  979.68  5577.5  976.99  5655.3  984.99  5878.6  985.34
#Mann=5,-1,0
  3617.6    0.05       0  4326.5    0.12       0  4696.2    0.05       0
  5002.1    0.05       0  5007.4    0.05       0
Bank Sta=5002.1,5007.4
Exp/Cntr=0.3,0.1

Type RM Length L Ch R = 1,1512,995,995,995
BEGIN DESCRIPTION:
MUD CREEK 3.0
END DESCRIPTION:
XS GIS Cut Line= 3
      2847678.03     10252942.77      2846308.50     10251754.00
      2845102.31     10251504.11
#Sta/Elev= 30
  3186.5  981.54  3350.6  981.53  3620.4  973.54  3896.7  970.82  3996.4  964.33
  4116.5  960.92  4598.5  952.88  4719.1  953.73  4839.7  948.61  4903.3  943.65
  4910.9  944.76  4917.6  943.30  4931.8  946.69  4952.7  945.13  4960.3  941.67
  4985.9  938.33  4986.3  937.83  4991.7  938.33  5013.1  939.01  5105.0  949.91
  5224.3  961.44  5319.5  964.31  5431.8  964.60  5475.2  962.86  5564.6  965.14
  5766.1  977.96  5922.0  994.93  5973.0  997.49  6117.3  997.82  6231.8  994.71
#Mann=3,-1,0
  3186.5    0.05       0  4985.9    0.03       0  4991.7    0.05       0
Bank Sta=4985.9,4991.7
Exp/Cntr=0.3,0.1

Type RM Length L Ch R = 1,517,0,0,0
BEGIN DESCRIPTION:
MUD CREEK 1.0
END DESCRIPTION:
XS GIS Cut Line= 4
      2847656.22     10251931.86      2846980.50     10251206.00
      2846929.07     10251047.81      2845234.77     10250753.61
#Sta/Elev= 30
  4008.3  981.92  4609.0  956.34  4708.2  953.93  4729.7  959.40  4814.2  959.63
  4878.2  943.62  4913.4  949.43  4920.7  944.83  4941.5  943.45  4949.1  938.17
  4955.9  941.21  4970.1  930.93  4976.9  933.88  4981.3  928.09  4981.8  927.59
  4987.3  928.09  5035.8  937.17  5067.7  949.08  5124.4  957.08  5266.2  960.68
  5418.4  966.48  5474.3  970.22  5512.5  966.68  5517.6  969.64  5555.5  963.36
  5697.6  965.53  5799.1  977.57  5925.9  969.02  6468.9  966.89  6886.0  985.07
#Mann=8,-1,0
  4008.3    0.05       0  4941.5    0.12       0  4981.3    0.07       0
  4987.3    0.12       0  5124.4    0.05       0  5266.2    0.05       0
  5418.4    0.05       0  5925.9    0.05       0
Bank Sta=4981.3,4987.3
Exp/Cntr=0.3,0.1

Chan Stop Cuts=-1