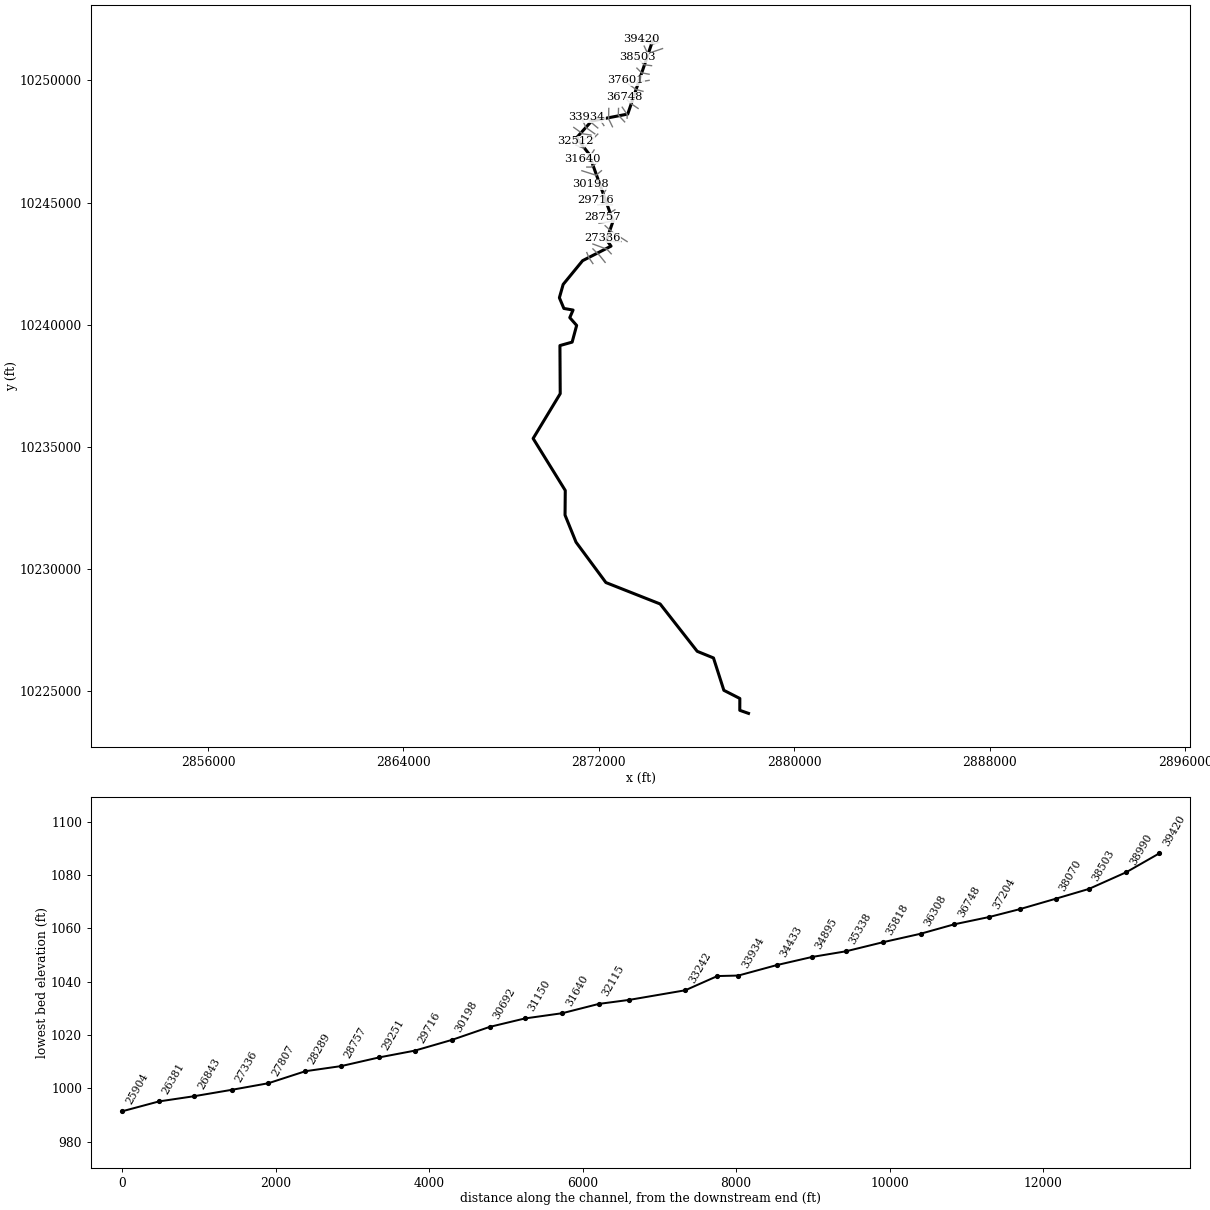
--- PENNINGTON CREEK.prj (project) ---

Proj Title=PENNINGTON CREEK Base Level Engineering
Current Plan=p01
Default Exp/Contr=0.3,0.1
English Units
Geom File=g01
Flow File=f01
Plan File=p01
BEGIN DESCRIPTION:
PENNINGTON CREEK
END DESCRIPTION:

--- PENNINGTON CREEK.p01 (plan) ---

Plan Title=Multiple Run
Short Identifier=Multiple
Geom File=g01
Flow File=f01
Subcritical Flow
K Sum by GR= 0
Std Step Tol= 0.01
Critical Tol= 0.01
Num of Std Step Trials= 20
Max Error Tol= 0.3
Flow Tol Ratio= 0.001
Split Flow NTrial= 30
Split Flow Tol= 0.02
Split Flow Ratio= 0.02
Log Output Level= 0
Friction Slope Method= 1
Unsteady Friction Slope Method= 2
Unsteady Bridges Friction Slope Method= 1
Parabolic Critical Depth
Global Vel Dist=  1 , 1 , 1
Global Log Level= 0
CheckData=True
Encroach Param= -1, 0, 0, 0
BEGIN DESCRIPTION:
Multiple Run
END DESCRIPTION:

--- PENNINGTON CREEK.f01 (steady flow) ---

Flow Title=Multiple
Number of Profiles=7
Profile Names=10-year,25-year,50-year,1pct_min,100-year,1pct_plu,500-year
River Rch & RM= PENNINGTON CREEK,Reach-1,39420
      64     124     195     101     306     923     806
River Rch & RM= PENNINGTON CREEK,Reach-1,23599
      73     145     229     120     362    1094     967
River Rch & RM= PENNINGTON CREEK,Reach-1,19306
     113     236     382     204     616    1861    1706
River Rch & RM= PENNINGTON CREEK,Reach-1,17826
     114     239     388     207     626    1891    1735
River Rch & RM= PENNINGTON CREEK,Reach-1,16209
     177     386     639     347    1048    3164    2994
River Rch & RM= PENNINGTON CREEK,Reach-1,11574
     206     454     755     412    1245    3759    3592
River Rch & RM= PENNINGTON CREEK,Reach-1,5395
     244     543     909     499    1506    4548    4389
River Rch & RM= PENNINGTON CREEK,Reach-1,4822
     393     902    1535     854    2579    7789    7719
River Rch & RM= PENNINGTON CREEK,Reach-1,721
     437    1009    1723     961    2903    8766    8734
Boundary for River Rch & Prof#=PENNINGTON CREEK,Reach-1,1
Up Type=0
Dn Type=3
Dn Slope=0.005
Boundary for River Rch & Prof#=PENNINGTON CREEK,Reach-1,2
Up Type=0
Dn Type=3
Dn Slope=0.005
Boundary for River Rch & Prof#=PENNINGTON CREEK,Reach-1,3
Up Type=0
Dn Type=3
Dn Slope=0.005
Boundary for River Rch & Prof#=PENNINGTON CREEK,Reach-1,4
Up Type=0
Dn Type=3
Dn Slope=0.005
Boundary for River Rch & Prof#=PENNINGTON CREEK,Reach-1,5
Up Type=0
Dn Type=3
Dn Slope=0.005
Boundary for River Rch & Prof#=PENNINGTON CREEK,Reach-1,6
Up Type=0
Dn Type=3
Dn Slope=0.005
Boundary for River Rch & Prof#=PENNINGTON CREEK,Reach-1,7
Up Type=0
Dn Type=3
Dn Slope=0.005

--- PENNINGTON CREEK.g01 (geometry) ---

Geom Title=Existing Conditions

River Reach=PENNINGTON CREEK,Reach-1
Reach XY= 30
      2874234.00     10251722.00      2873182.25     10248623.00
      2871704.50     10248338.00      2871085.25     10247652.00
      2871589.25     10246999.00      2872581.25     10244242.00
      2872315.25     10243469.00      2872498.00     10243217.00
      2871334.25     10242622.00      2870538.75     10241650.00
      2870383.50     10241105.00      2870568.00     10240666.00
      2870943.75     10240600.00      2870809.25     10240291.00
      2871090.00     10239971.00      2870906.00     10239288.00
      2870406.00     10239147.00      2870418.00     10237178.00
      2869309.00     10235344.00      2870624.75     10233216.00
      2870615.25     10232208.00      2871065.00     10231100.00
      2872287.25     10229447.00      2874508.00     10228570.00
      2876025.50     10226632.00      2876691.00     10226361.00
      2877116.00     10225036.00      2877769.75     10224702.00
      2877767.75     10224217.00      2878124.50     10224092.00

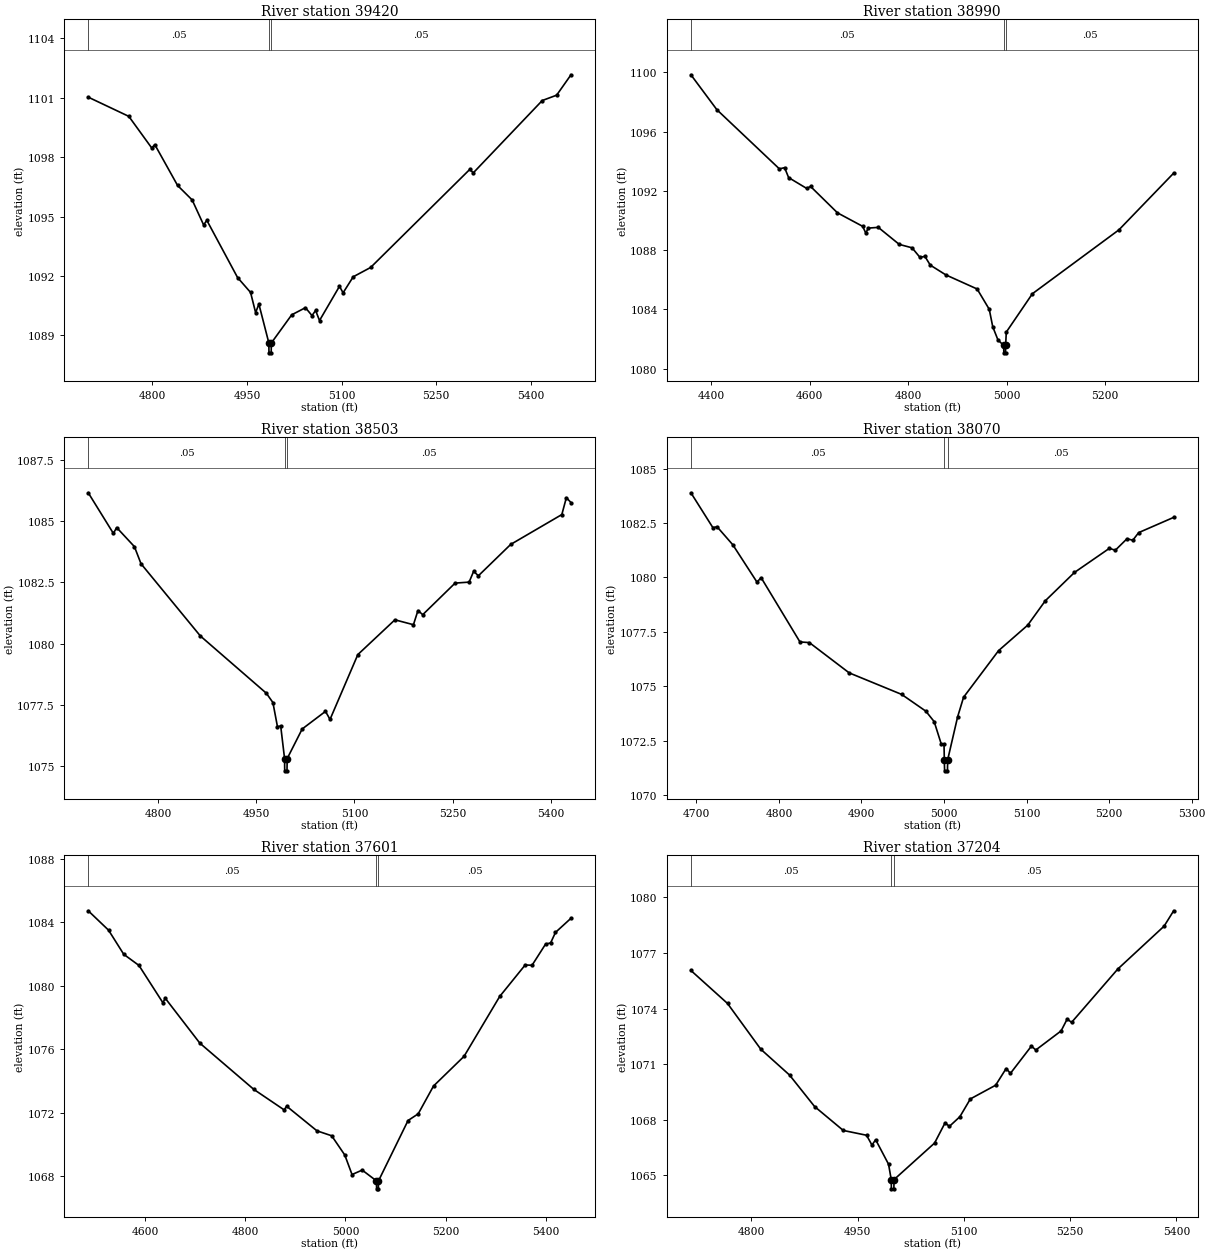
Type RM Length L Ch R = 1,39420,430,430,430
BEGIN DESCRIPTION:
PENNINGTON CREEK 74.0
END DESCRIPTION:
XS GIS Cut Line= 3
      2874455.66     10251553.11      2874162.75     10251480.00
      2873755.68     10251703.11
#Sta/Elev= 30
  4698.1 1101.03  4762.5 1100.06  4798.7 1098.47  4803.8 1098.63  4839.9 1096.57
  4863.0 1095.84  4881.2 1094.58  4886.3 1094.81  4935.1 1091.92  4955.7 1091.17
  4963.7 1090.15  4968.9 1090.58  4984.7 1088.62  4984.9 1088.12  4988.4 1088.12
  4988.7 1088.62  5021.0 1090.04  5042.8 1090.40  5053.2 1090.00  5058.9 1090.26
  5065.1 1089.75  5096.8 1091.48  5102.5 1091.15  5118.6 1091.96  5146.2 1092.43
  5303.5 1097.38  5309.2 1097.21  5418.6 1100.86  5441.4 1101.13  5464.2 1102.16
#Mann=3,-1,0
  4698.1    0.05       0  4984.7    0.03       0  4988.7    0.05       0
Bank Sta=4984.7,4988.7
Exp/Cntr=0.3,0.1

Type RM Length L Ch R = 1,38990,487,487,487
BEGIN DESCRIPTION:
PENNINGTON CREEK 73.0
END DESCRIPTION:
XS GIS Cut Line= 3
      2874605.69     10251303.11      2873998.75     10251096.00
      2873855.68     10251403.11
#Sta/Elev= 30
  4358.7 1099.83  4411.5 1097.47  4538.3 1093.48  4548.9 1093.56  4557.1 1092.89
  4593.7 1092.16  4601.7 1092.29  4656.3 1090.51  4707.4 1089.60  4713.7 1089.15
  4719.0 1089.48  4739.1 1089.53  4781.7 1088.38  4807.7 1088.15  4823.6 1087.51
  4833.8 1087.57  4844.7 1086.98  4876.4 1086.32  4939.8 1085.37  4964.4 1084.00
  4971.5 1082.82  4982.1 1081.93  4993.7 1081.56  4994.0 1081.06  4997.5 1081.06
  4997.7 1081.56  4999.0 1082.46  5052.0 1085.05  5227.6 1089.36  5338.8 1093.19
#Mann=3,-1,0
  4358.7    0.05       0  4993.7    0.03       0  4997.7    0.05       0
Bank Sta=4993.7,4997.7
Exp/Cntr=0.3,0.1

Type RM Length L Ch R = 1,38503,433,433,433
BEGIN DESCRIPTION:
PENNINGTON CREEK 72.0
END DESCRIPTION:
XS GIS Cut Line= 3
      2874155.67     10250603.11      2873851.50     10250640.00
      2873555.65     10250953.15
#Sta/Elev= 30
  4693.6 1086.16  4732.0 1084.50  4737.0 1084.74  4764.1 1083.96  4774.2 1083.26
  4864.8 1080.31  4965.6 1077.97  4975.6 1077.59  4982.5 1076.61  4987.5 1076.63
  4993.4 1075.30  4993.6 1074.80  4997.1 1074.80  4997.4 1075.30  5020.3 1076.51
  5055.9 1077.23  5062.8 1076.90  5105.3 1079.55  5161.9 1080.97  5190.2 1080.77
  5197.1 1081.35  5204.4 1081.18  5253.8 1082.47  5275.2 1082.51  5282.1 1082.95
  5289.4 1082.77  5338.7 1084.05  5416.8 1085.27  5423.7 1085.96  5430.8 1085.76
#Mann=3,-1,0
  4693.6    0.05       0  4993.4    0.05       0  4997.4    0.05       0
Bank Sta=4993.4,4997.4
Exp/Cntr=0.3,0.1

Type RM Length L Ch R = 1,38070,469,469,469
BEGIN DESCRIPTION:
PENNINGTON CREEK 71.0
END DESCRIPTION:
XS GIS Cut Line= 3
      2874055.65     10250253.12      2873754.00     10250308.00
      2873555.69     10250503.11
#Sta/Elev= 30
  4693.4 1083.89  4720.0 1082.29  4725.1 1082.33  4744.2 1081.50  4773.4 1079.79
  4778.5 1079.99  4825.5 1077.04  4836.9 1077.01  4885.1 1075.62  4948.7 1074.63
  4978.0 1073.86  4988.1 1073.38  4996.6 1072.36  5000.0 1072.36  5000.4 1071.62
  5000.7 1071.12  5004.2 1071.12  5004.4 1071.62  5016.5 1073.60  5023.7 1074.50
  5066.1 1076.64  5101.4 1077.81  5122.7 1078.93  5158.0 1080.23  5200.4 1081.34
  5207.5 1081.25  5221.7 1081.78  5228.7 1081.71  5235.8 1082.06  5278.2 1082.76
#Mann=3,-1,0
  4693.4    0.05       0  5000.4    0.03       0  5004.4    0.05       0
Bank Sta=5000.4,5004.4
Exp/Cntr=0.3,0.1

Type RM Length L Ch R = 1,37601,397,397,397
BEGIN DESCRIPTION:
PENNINGTON CREEK 70.0
END DESCRIPTION:
XS GIS Cut Line= 3
      2874055.71     10250003.12      2873548.50     10249918.00
      2873105.70     10250003.11
#Sta/Elev= 30
  4485.7 1084.71  4526.3 1083.49  4556.7 1081.97  4587.1 1081.27  4634.8 1078.93
  4639.8 1079.20  4708.8 1076.38  4816.7 1073.47  4877.3 1072.18  4882.4 1072.41
  4943.0 1070.86  4972.4 1070.55  4998.6 1069.34  5013.1 1068.11  5033.4 1068.39
  5062.0 1067.71  5062.2 1067.21  5065.7 1067.21  5066.0 1067.71  5125.1 1071.51
  5145.4 1071.93  5176.0 1073.68  5237.1 1075.55  5308.4 1079.32  5359.3 1081.30
  5373.0 1081.28  5400.0 1082.61  5410.2 1082.69  5419.9 1083.35  5450.9 1084.24
#Mann=3,-1,0
  4485.7    0.05       0  5062.0    0.03       0  5066.0    0.05       0
Bank Sta=5062,5066
Exp/Cntr=0.3,0.1

Type RM Length L Ch R = 1,37204,456,456,456
BEGIN DESCRIPTION:
PENNINGTON CREEK 69.0
END DESCRIPTION:
XS GIS Cut Line= 3
      2873805.70     10249553.11      2873529.50     10249625.00
      2873205.68     10249853.11
#Sta/Elev= 30
  4714.6 1076.06  4766.3 1074.28  4813.3 1071.81  4853.8 1070.42  4889.2 1068.72
  4929.7 1067.43  4962.6 1067.17  4970.2 1066.64  4975.4 1066.93  4993.6 1065.61
  4997.4 1064.78  4997.6 1064.28  5001.1 1064.28  5001.4 1064.78  5058.6 1066.75
  5073.4 1067.84  5079.5 1067.65  5094.3 1068.17  5109.1 1069.13  5144.8 1069.87
  5159.6 1070.77  5165.7 1070.51  5195.3 1071.98  5201.5 1071.77  5237.2 1072.80
  5245.8 1073.44  5252.0 1073.26  5317.3 1076.14  5382.6 1078.45  5396.1 1079.28
#Mann=3,-1,0
  4714.6    0.05       0  4997.4    0.03       0  5001.4    0.05       0
Bank Sta=4997.4,5001.4
Exp/Cntr=0.3,0.1

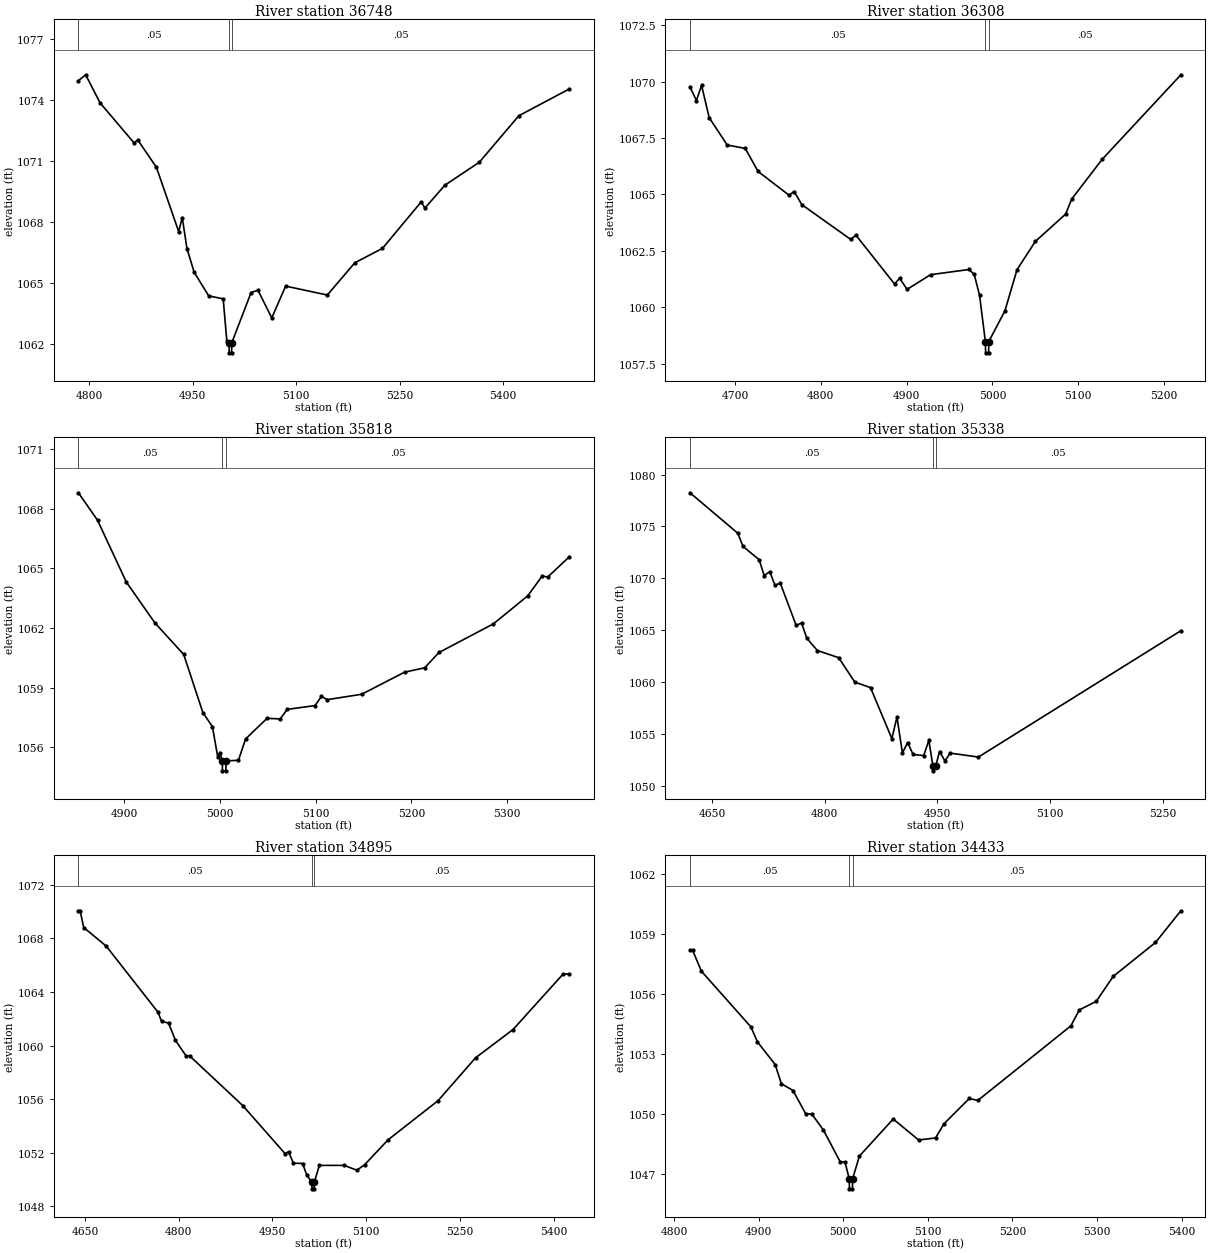
Type RM Length L Ch R = 1,36748,440,440,440
BEGIN DESCRIPTION:
PENNINGTON CREEK 68.0
END DESCRIPTION:
XS GIS Cut Line= 3
      2873755.68     10249403.11      2873550.25     10249338.00
      2873055.68     10249303.11
#Sta/Elev= 30
  4784.5 1074.96  4795.0 1075.25  4816.0 1073.86  4865.2 1071.89  4870.5 1072.04
  4897.5 1070.69  4929.8 1067.52  4935.0 1068.21  4941.8 1066.68  4952.3 1065.51
  4973.3 1064.35  4994.3 1064.20  4999.6 1062.12  5002.8 1062.04  5003.0 1061.54
  5006.5 1061.54  5006.8 1062.04  5034.7 1064.51  5044.7 1064.63  5064.7 1063.26
  5084.8 1064.83  5145.2 1064.39  5185.0 1065.98  5225.1 1066.69  5281.4 1068.99
  5286.5 1068.67  5315.3 1069.80  5365.5 1070.94  5422.7 1073.23  5495.8 1074.55
#Mann=3,-1,0
  4784.5    0.05       0  5002.8    0.05       0  5006.8    0.05       0
Bank Sta=5002.8,5006.8
Exp/Cntr=0.3,0.1

Type RM Length L Ch R = 1,36308,490,490,490
BEGIN DESCRIPTION:
PENNINGTON CREEK 67.0
END DESCRIPTION:
XS GIS Cut Line= 3
      2873605.65     10248853.13      2873313.25     10249050.00
      2873155.69     10249203.11
#Sta/Elev= 30
  4647.5 1069.76  4655.0 1069.16  4661.0 1069.83  4669.9 1068.40  4690.9 1067.19
  4711.9 1067.04  4726.9 1066.02  4762.9 1064.97  4768.9 1065.13  4777.9 1064.55
  4834.9 1063.01  4840.9 1063.20  4885.9 1061.04  4891.9 1061.29  4900.6 1060.80
  4927.9 1061.45  4972.8 1061.68  4978.8 1061.46  4985.0 1060.55  4991.8 1058.49
  4992.1 1057.99  4995.6 1057.99  4995.8 1058.49  5014.6 1059.85  5028.7 1061.67
  5050.0 1062.92  5085.3 1064.13  5092.5 1064.80  5127.8 1066.55  5219.7 1070.30
#Mann=3,-1,0
  4647.5    0.05       0  4991.8    0.05       0  4995.8    0.05       0
Bank Sta=4991.8,4995.8
Exp/Cntr=0.3,0.1

Type RM Length L Ch R = 1,35818,480,480,480
BEGIN DESCRIPTION:
PENNINGTON CREEK 66.0
END DESCRIPTION:
XS GIS Cut Line= 3
      2873155.68     10248453.09      2873160.75     10248601.00
      2872955.70     10248903.08
#Sta/Elev= 30
  4852.0 1068.80  4872.0 1067.42  4902.1 1064.31  4932.1 1062.25  4962.1 1060.67
  4982.1 1057.75  4992.1 1057.04  4997.6 1055.53  5000.0 1055.74  5002.4 1055.32
  5002.6 1054.82  5006.1 1054.82  5006.4 1055.32  5019.3 1055.35  5026.7 1056.42
  5049.2 1057.46  5063.0 1057.43  5070.2 1057.91  5099.2 1058.10  5106.1 1058.56
  5112.2 1058.40  5148.1 1058.67  5192.9 1059.78  5213.9 1060.00  5228.9 1060.77
  5285.8 1062.21  5321.7 1063.62  5336.7 1064.61  5342.7 1064.57  5365.1 1065.58
#Mann=3,-1,0
  4852.0    0.05       0  5002.4    0.03       0  5006.4    0.05       0
Bank Sta=5002.4,5006.4
Exp/Cntr=0.3,0.1

Type RM Length L Ch R = 1,35338,443,443,443
BEGIN DESCRIPTION:
PENNINGTON CREEK 65.0
END DESCRIPTION:
XS GIS Cut Line= 3
      2873055.71     10248303.09      2872795.00     10248579.00
      2872805.68     10248853.09
#Sta/Elev= 30
  4620.4 1078.24  4684.1 1074.34  4691.0 1073.07  4712.5 1071.79  4719.3 1070.25
  4726.6 1070.64  4733.5 1069.35  4740.8 1069.50  4761.8 1065.46  4769.1 1065.68
  4776.0 1064.21  4790.1 1063.03  4818.5 1062.34  4839.9 1059.99  4860.9 1059.45
  4889.3 1054.54  4896.1 1056.61  4903.4 1053.15  4910.3 1054.16  4917.6 1053.01
  4931.7 1052.90  4938.6 1054.37  4943.9 1051.93  4944.1 1051.43  4947.9 1051.93
  4952.8 1053.29  4960.1 1052.38  4966.9 1053.14  5004.6 1052.76  5274.3 1064.94
#Mann=3,-1,0
  4620.4    0.05       0  4943.9    0.03       0  4947.9    0.05       0
Bank Sta=4943.9,4947.9
Exp/Cntr=0.3,0.1

Type RM Length L Ch R = 1,34895,462,462,462
BEGIN DESCRIPTION:
PENNINGTON CREEK 64.0
END DESCRIPTION:
XS GIS Cut Line= 3
      2872555.69     10248103.10      2872399.25     10248428.00
      2872405.68     10248853.15
#Sta/Elev= 30
  4639.4 1070.06  4642.2 1070.06  4647.9 1068.81  4683.8 1067.43  4766.6 1062.50
  4772.6 1061.80  4783.7 1061.68  4794.8 1060.38  4811.9 1059.22  4817.4 1059.23
  4902.4 1055.52  4970.2 1051.93  4975.8 1052.07  4983.5 1051.22  4998.3 1051.19
  5005.1 1050.31  5013.1 1049.80  5013.4 1049.30  5016.9 1049.30  5017.1 1049.80
  5025.1 1051.05  5065.1 1051.05  5085.1 1050.69  5097.4 1051.09  5135.1 1052.96
  5215.1 1055.88  5275.1 1059.08  5335.1 1061.19  5415.2 1065.33  5425.2 1065.35
#Mann=3,-1,0
  4639.4    0.05       0  5013.1    0.03       0  5017.1    0.05       0
Bank Sta=5013.1,5017.1
Exp/Cntr=0.3,0.1

Type RM Length L Ch R = 1,34433,499,499,499
BEGIN DESCRIPTION:
PENNINGTON CREEK 63.0
END DESCRIPTION:
XS GIS Cut Line= 3
      2872205.67     10248153.13      2872105.50     10248304.00
      2872105.68     10248703.10
#Sta/Elev= 30
  4818.9 1058.21  4821.9 1058.21  4832.4 1057.15  4890.9 1054.36  4898.6 1053.61
  4919.6 1052.47  4926.9 1051.51  4940.7 1051.17  4955.7 1050.00  4962.9 1049.99
  4976.7 1049.18  4996.5 1047.59  5002.1 1047.59  5007.1 1046.74  5007.4 1046.24
  5010.9 1046.24  5011.1 1046.74  5019.1 1047.88  5059.1 1049.74  5089.1 1048.69
  5109.1 1048.79  5119.1 1049.50  5149.1 1050.77  5159.1 1050.67  5269.1 1054.41
  5279.1 1055.21  5299.1 1055.64  5319.1 1056.89  5369.1 1058.59  5399.1 1060.18
#Mann=3,-1,0
  4818.9    0.05       0  5007.1    0.03       0  5011.1    0.05       0
Bank Sta=5007.1,5011.1
Exp/Cntr=0.3,0.1

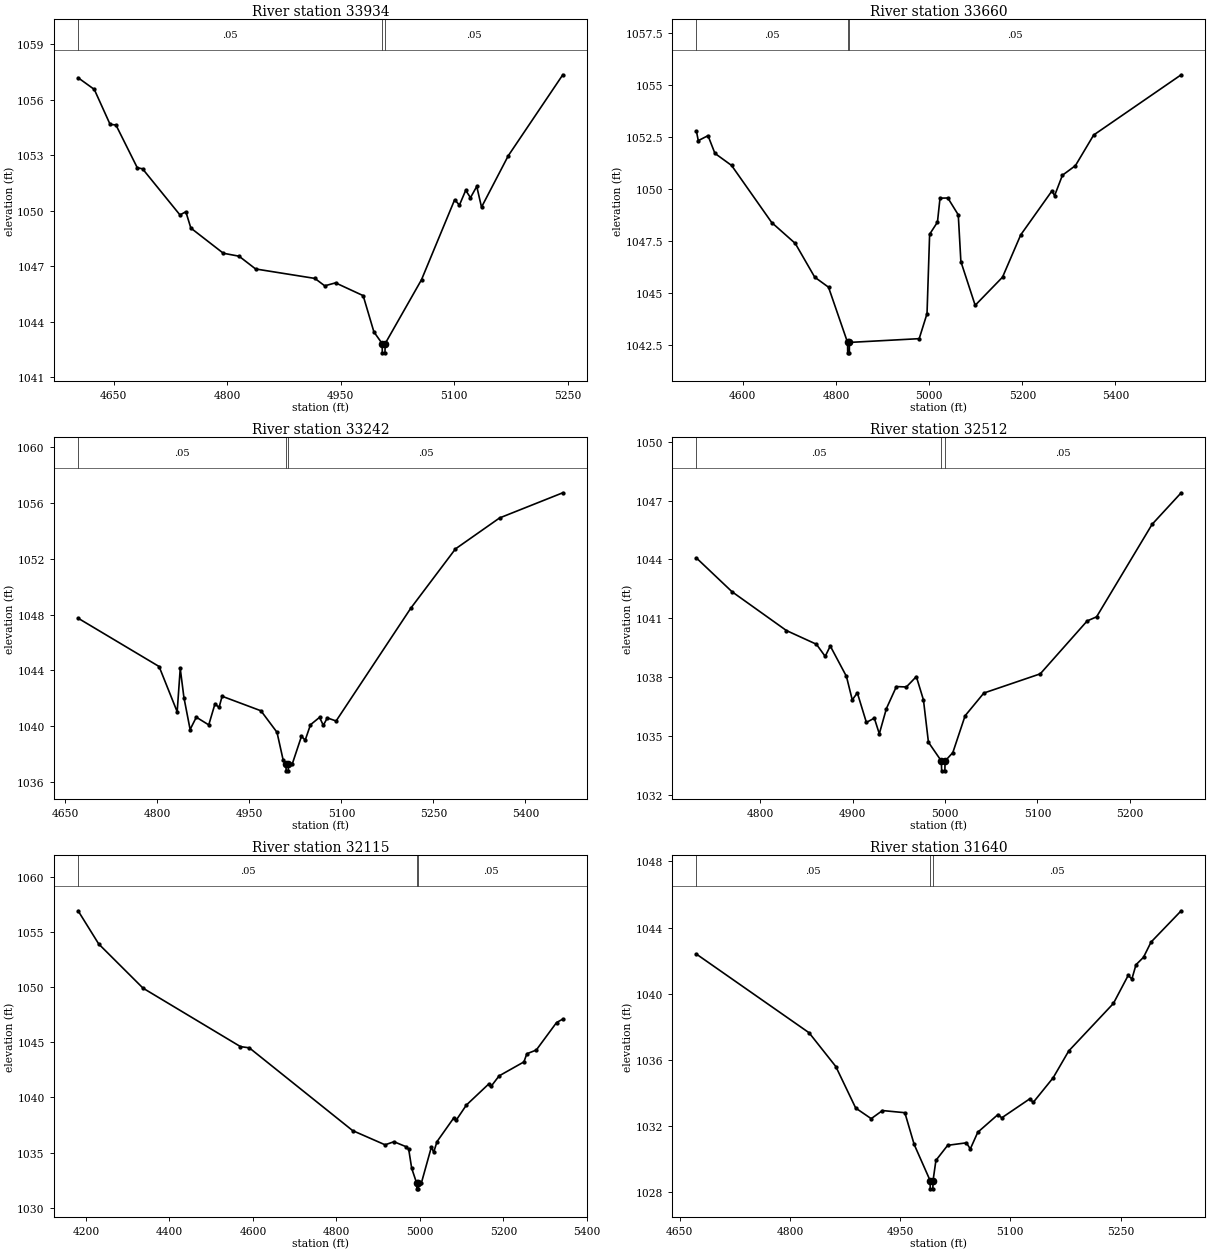
Type RM Length L Ch R = 1,33934,274,274,274
BEGIN DESCRIPTION:
PENNINGTON CREEK 62.0
END DESCRIPTION:
XS GIS Cut Line= 3
      2871955.65     10248053.14      2871651.00     10248308.00
      2871505.67     10248503.13
#Sta/Elev= 30
  4602.8 1057.19  4624.2 1056.56  4645.1 1054.67  4652.8 1054.64  4681.0 1052.33
  4688.0 1052.27  4737.4 1049.78  4745.2 1049.95  4751.8 1049.07  4794.7 1047.71
  4815.5 1047.55  4837.4 1046.86  4915.7 1046.35  4928.7 1045.95  4943.0 1046.11
  4979.5 1045.42  4993.7 1043.46  5004.6 1042.83  5004.8 1042.33  5008.3 1042.33
  5008.6 1042.83  5056.6 1046.28  5100.4 1050.60  5106.7 1050.31  5115.0 1051.11
  5121.3 1050.71  5129.6 1051.32  5135.9 1050.20  5171.3 1052.98  5243.3 1057.35
#Mann=3,-1,0
  4602.8    0.05       0  5004.6    0.03       0  5008.6    0.05       0
Bank Sta=5004.6,5008.6
Exp/Cntr=0.3,0.1

Type RM Length L Ch R = 1,33660,418,418,418
BEGIN DESCRIPTION:
Mapping XS 4f6b9a04
END DESCRIPTION:
XS GIS Cut Line= 3
      2871832.62     10247814.97      2871481.02     10248062.39
      2871207.87     10248608.68
#Sta/Elev= 30
  4500.4 1052.76  4504.3 1052.32  4525.2 1052.56  4540.0 1051.71  4575.8 1051.13
  4662.0 1048.39  4712.5 1047.39  4754.3 1045.77  4783.9 1045.29  4824.8 1042.64
  4825.1 1042.14  4828.6 1042.14  4828.8 1042.64  4978.6 1042.82  4995.4 1044.02
  5001.0 1047.83  5017.8 1048.41  5023.3 1049.56  5040.1 1049.57  5062.5 1048.76
  5068.1 1046.52  5098.8 1044.42  5157.5 1045.77  5196.6 1047.80  5263.7 1049.91
  5269.3 1049.68  5286.1 1050.66  5314.0 1051.12  5353.2 1052.59  5541.1 1055.48
#Mann=3,-1,0
  4500.4    0.05       0  4824.8    0.05       0  4828.8    0.05       0
Bank Sta=4824.8,4828.8
Exp/Cntr=0.3,0.1

Type RM Length L Ch R = 1,33242,730,730,730
BEGIN DESCRIPTION:
Mapping XS 977c59ce
END DESCRIPTION:
XS GIS Cut Line= 3
      2871676.29     10247762.92      2871337.79     10247814.99
      2870973.22     10248075.40
#Sta/Elev= 30
  4670.6 1047.74  4802.7 1044.28  4832.2 1041.04  4837.2 1044.14  4843.2 1042.06
  4853.3 1039.77  4863.4 1040.65  4883.7 1040.10  4893.8 1041.60  4900.5 1041.35
  4905.5 1042.15  4968.8 1041.11  4995.0 1039.57  5005.1 1037.57  5009.6 1037.31
  5009.9 1036.81  5013.4 1036.81  5013.6 1037.31  5020.1 1037.33  5034.9 1039.28
  5041.0 1039.01  5049.6 1040.11  5064.4 1040.64  5070.5 1040.07  5077.1 1040.60
  5091.4 1040.38  5213.1 1048.45  5286.0 1052.70  5358.1 1054.92  5461.1 1056.72
#Mann=3,-1,0
  4670.6    0.05       0  5009.6    0.05       0  5013.6    0.05       0
Bank Sta=5009.6,5013.6
Exp/Cntr=0.3,0.1

Type RM Length L Ch R = 1,32512,397,397,397
BEGIN DESCRIPTION:
PENNINGTON CREEK 60.0
END DESCRIPTION:
XS GIS Cut Line= 3
      2871555.67     10247653.11      2871307.00     10247550.00
      2871055.64     10247503.10
#Sta/Elev= 30
  4730.8 1044.07  4769.3 1042.35  4828.2 1040.37  4860.7 1039.67  4870.2 1039.05
  4875.7 1039.58  4893.2 1038.03  4899.5 1036.83  4905.0 1037.19  4914.8 1035.68
  4923.4 1035.90  4928.8 1035.10  4936.5 1036.39  4947.3 1037.51  4958.1 1037.49
  4968.9 1038.02  4976.6 1036.83  4982.0 1034.67  4996.0 1033.71  4996.3 1033.21
  4999.8 1033.21  5000.0 1033.71  5008.4 1034.14  5021.7 1036.02  5042.0 1037.18
  5103.1 1038.16  5153.9 1040.86  5164.1 1041.07  5224.2 1045.79  5255.7 1047.40
#Mann=3,-1,0
  4730.8    0.05       0  4996.0    0.05       0  5000.0    0.05       0
Bank Sta=4996,5000
Exp/Cntr=0.3,0.1

Type RM Length L Ch R = 1,32115,475,475,475
BEGIN DESCRIPTION:
PENNINGTON CREEK 59.0
END DESCRIPTION:
XS GIS Cut Line= 3
      2871955.70     10247803.13      2871373.75     10247227.00
      2871055.64     10247353.13
#Sta/Elev= 30
  4181.1 1056.96  4230.6 1053.94  4336.7 1049.93  4570.1 1044.62  4591.2 1044.51
  4838.8 1036.99  4916.5 1035.70  4937.8 1035.98  4966.0 1035.54  4973.1 1035.29
  4980.2 1033.57  4992.3 1032.20  4992.6 1031.70  4996.1 1031.70  4996.3 1032.20
  5003.2 1032.20  5027.5 1035.51  5032.9 1035.02  5040.9 1035.99  5081.5 1038.17
  5086.9 1037.94  5111.2 1039.31  5165.2 1041.24  5170.6 1041.02  5189.6 1041.96
  5249.0 1043.23  5256.1 1043.97  5278.7 1044.31  5327.3 1046.81  5342.2 1047.12
#Mann=3,-1,0
  4181.1    0.05       0  4992.3    0.05       0  4996.3    0.05       0
Bank Sta=4992.3,4996.3
Exp/Cntr=0.3,0.1

Type RM Length L Ch R = 1,31640,490,490,490
BEGIN DESCRIPTION:
PENNINGTON CREEK 58.0
END DESCRIPTION:
XS GIS Cut Line= 3
      2871805.70     10247153.14      2871630.00     10246877.00
      2871305.71     10246803.12
#Sta/Elev= 30
  4672.7 1042.40  4826.0 1037.65  4862.4 1035.61  4889.5 1033.10  4910.6 1032.46
  4925.9 1032.95  4956.4 1032.82  4969.1 1030.90  4990.8 1028.72  4991.0 1028.22
  4994.5 1028.22  4994.8 1028.72  4998.7 1029.94  5014.7 1030.85  5040.2 1031.00
  5045.5 1030.63  5055.7 1031.64  5083.2 1032.71  5088.3 1032.51  5126.2 1033.65
  5131.3 1033.45  5158.3 1034.93  5179.5 1036.55  5240.3 1039.42  5260.4 1041.11
  5265.5 1040.90  5271.1 1041.76  5281.3 1042.21  5291.6 1043.13  5332.6 1045.02
#Mann=3,-1,0
  4672.7    0.05       0  4990.8    0.05       0  4994.8    0.05       0
Bank Sta=4990.8,4994.8
Exp/Cntr=0.3,0.1

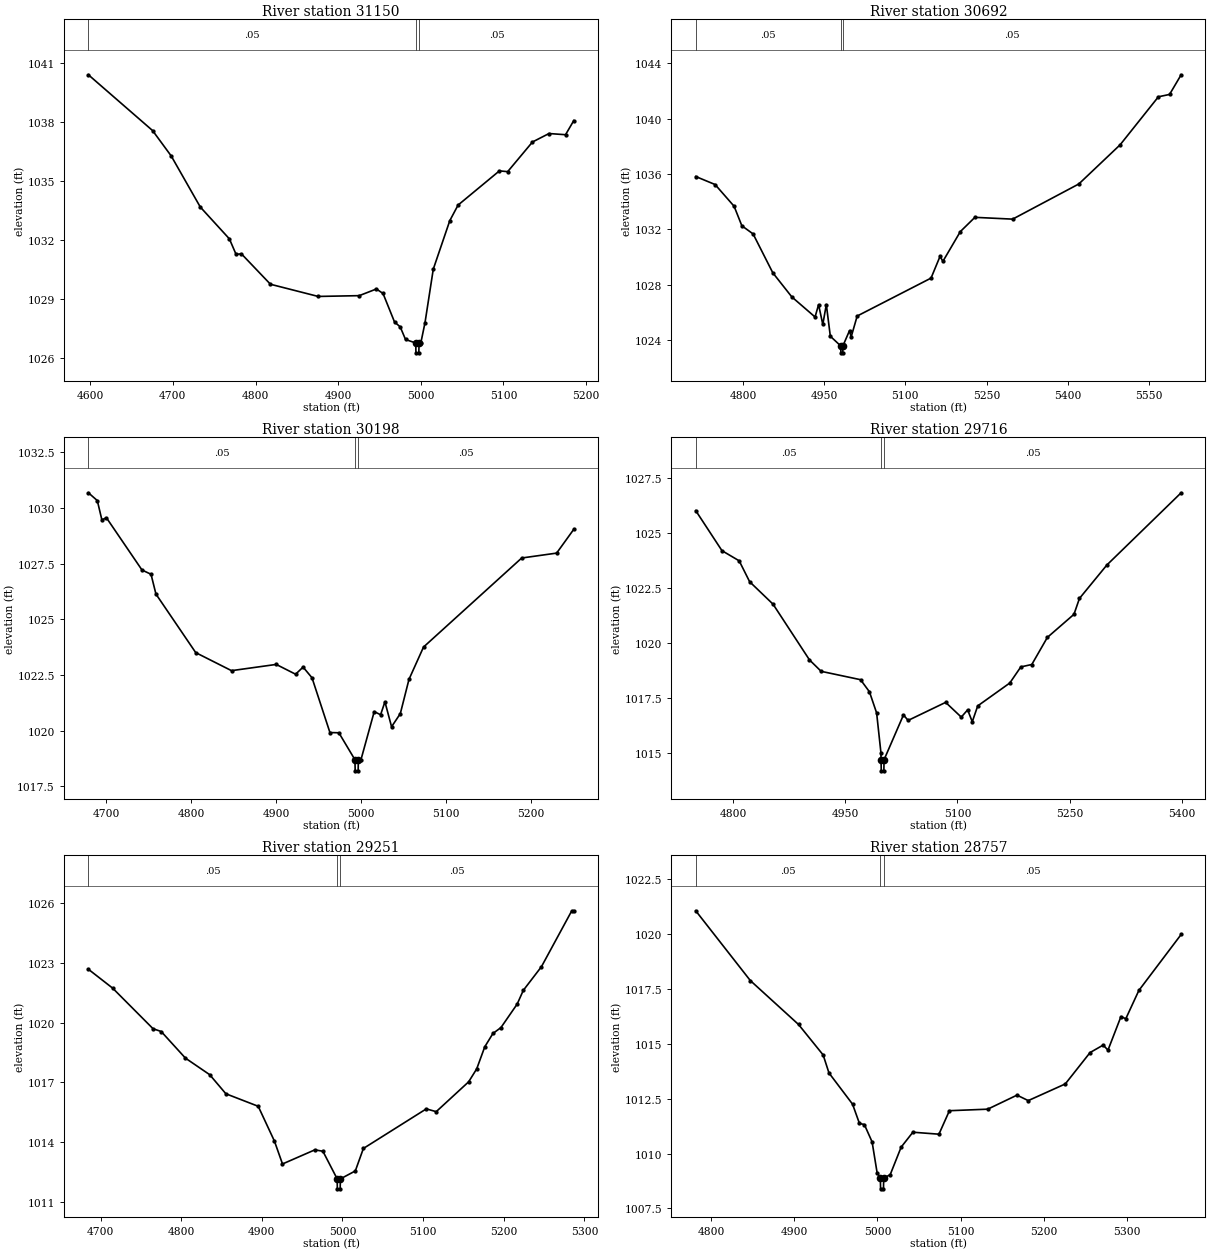
Type RM Length L Ch R = 1,31150,458,458,458
BEGIN DESCRIPTION:
PENNINGTON CREEK 57.0
END DESCRIPTION:
XS GIS Cut Line= 3
      2872005.71     10246703.13      2871690.75     10246453.00
      2871505.65     10246453.11
#Sta/Elev= 30
  4597.8 1040.39  4675.5 1037.55  4698.0 1036.26  4733.2 1033.66  4768.4 1032.04
  4776.5 1031.25  4782.9 1031.28  4818.1 1029.73  4875.8 1029.11  4925.5 1029.15
  4946.3 1029.49  4954.3 1029.26  4968.2 1027.81  4975.1 1027.56  4981.5 1026.92
  4993.9 1026.74  4994.1 1026.24  4997.6 1026.24  4997.9 1026.74  5000.0 1026.74
  5005.1 1027.78  5015.1 1030.50  5035.1 1032.97  5045.1 1033.76  5095.1 1035.50
  5105.1 1035.46  5135.1 1036.97  5155.1 1037.40  5175.1 1037.34  5185.1 1038.06
#Mann=3,-1,0
  4597.8    0.05       0  4993.9    0.05       0  4997.9    0.05       0
Bank Sta=4993.9,4997.9
Exp/Cntr=0.3,0.1

Type RM Length L Ch R = 1,30692,494,494,494
BEGIN DESCRIPTION:
PENNINGTON CREEK 56.0
END DESCRIPTION:
XS GIS Cut Line= 3
      2872105.70     10246303.12      2871886.25     10246118.00
      2871305.65     10246303.12
#Sta/Elev= 30
  4712.9 1035.82  4748.7 1035.24  4783.8 1033.67  4798.1 1032.26  4818.9 1031.67
  4855.3 1028.86  4890.4 1027.12  4933.3 1025.67  4939.8 1026.56  4947.6 1025.13
  4954.1 1026.57  4961.5 1024.28  4980.7 1023.58  4981.0 1023.08  4984.5 1023.08
  4984.7 1023.58  4997.0 1024.69  4999.9 1024.22  5011.1 1025.74  5147.5 1028.48
  5164.1 1030.05  5169.4 1029.69  5201.6 1031.84  5228.5 1032.87  5298.2 1032.74
  5420.4 1035.28  5496.7 1038.11  5567.4 1041.58  5588.0 1041.75  5609.4 1043.17
#Mann=3,-1,0
  4712.9    0.05       0  4980.7    0.03       0  4984.7    0.05       0
Bank Sta=4980.7,4984.7
Exp/Cntr=0.3,0.1

Type RM Length L Ch R = 1,30198,482,482,482
BEGIN DESCRIPTION:
PENNINGTON CREEK 55.0
END DESCRIPTION:
XS GIS Cut Line= 3
      2872205.67     10245803.11      2871901.00     10245703.00
      2871655.67     10245753.12
#Sta/Elev= 30
  4679.3 1030.68  4689.8 1030.33  4695.2 1029.46  4700.5 1029.56  4742.4 1027.21
  4753.0 1027.02  4758.8 1026.13  4805.6 1023.50  4847.7 1022.69  4900.3 1022.97
  4923.1 1022.53  4931.9 1022.85  4942.4 1022.37  4963.5 1019.91  4974.0 1019.90
  4992.9 1018.69  4993.2 1018.19  4996.7 1018.19  4996.9 1018.69  5000.0 1018.69
  5015.6 1020.85  5023.1 1020.71  5028.2 1021.29  5036.0 1020.17  5046.3 1020.76
  5056.5 1022.30  5073.6 1023.75  5189.1 1027.75  5230.2 1027.97  5250.4 1029.04
#Mann=3,-1,0
  4679.3    0.05       0  4992.9    0.05       0  4996.9    0.05       0
Bank Sta=4992.9,4996.9
Exp/Cntr=0.3,0.1

Type RM Length L Ch R = 1,29716,465,465,465
BEGIN DESCRIPTION:
PENNINGTON CREEK 54.0
END DESCRIPTION:
XS GIS Cut Line= 3
      2872305.69     10245553.11      2872178.50     10245338.00
      2871855.71     10245103.13
#Sta/Elev= 30
  4750.1 1026.00  4785.2 1024.18  4808.2 1023.72  4822.2 1022.77  4853.5 1021.75
  4902.2 1019.22  4917.8 1018.70  4970.5 1018.32  4982.4 1017.77  4992.0 1016.81
  4997.8 1014.99  4997.9 1014.68  4998.2 1014.18  5001.7 1014.18  5001.9 1014.68
  5027.9 1016.72  5034.1 1016.47  5084.3 1017.29  5105.2 1016.62  5113.7 1016.95
  5119.9 1016.41  5127.2 1017.13  5170.1 1018.17  5184.8 1018.90  5199.5 1019.01
  5220.3 1020.24  5255.9 1021.29  5263.2 1022.01  5299.9 1023.53  5399.2 1026.81
#Mann=3,-1,0
  4750.1    0.05       0  4997.9    0.03       0  5001.9    0.05       0
Bank Sta=4997.9,5001.9
Exp/Cntr=0.3,0.1

Type RM Length L Ch R = 1,29251,494,494,494
BEGIN DESCRIPTION:
PENNINGTON CREEK 53.0
END DESCRIPTION:
XS GIS Cut Line= 3
      2872555.69     10244903.11      2872241.50     10244927.00
      2871955.70     10244903.11
#Sta/Elev= 30
  4684.9 1022.68  4715.0 1021.73  4765.1 1019.69  4775.2 1019.55  4805.3 1018.21
  4835.3 1017.38  4855.4 1016.42  4895.5 1015.79  4915.6 1014.04  4925.6 1012.89
  4965.7 1013.60  4975.7 1013.53  4993.4 1012.14  4993.6 1011.64  4997.1 1011.64
  4997.4 1012.14  5015.9 1012.54  5025.9 1013.67  5103.9 1015.66  5116.2 1015.52
  5156.4 1017.02  5166.4 1017.67  5176.4 1018.78  5186.5 1019.45  5196.5 1019.75
  5216.6 1020.93  5224.2 1021.62  5246.7 1022.81  5284.3 1025.62  5286.8 1025.62
#Mann=3,-1,0
  4684.9    0.05       0  4993.4    0.03       0  4997.4    0.05       0
Bank Sta=4993.4,4997.4
Exp/Cntr=0.3,0.1

Type RM Length L Ch R = 1,28757,468,468,468
BEGIN DESCRIPTION:
PENNINGTON CREEK 52.0
END DESCRIPTION:
XS GIS Cut Line= 3
      2872655.72     10244703.13      2872470.25     10244588.00
      2872155.66     10244403.10
#Sta/Elev= 30
  4781.7 1021.06  4847.3 1017.88  4905.2 1015.88  4934.8 1014.49  4941.8 1013.67
  4970.1 1012.25  4978.4 1011.37  4984.3 1011.32  4993.6 1010.53  4999.6 1009.13
  5003.5 1008.89  5003.8 1008.39  5007.3 1008.39  5007.5 1008.89  5015.3 1009.03
  5028.5 1010.29  5042.6 1010.97  5073.9 1010.88  5086.5 1011.95  5132.5 1012.02
  5167.7 1012.66  5181.2 1012.41  5225.7 1013.17  5255.5 1014.60  5271.2 1014.94
  5277.0 1014.71  5292.6 1016.24  5298.4 1016.14  5314.1 1017.43  5364.9 1019.98
#Mann=3,-1,0
  4781.7    0.05       0  5003.5    0.03       0  5007.5    0.05       0
Bank Sta=5003.5,5007.5
Exp/Cntr=0.3,0.1

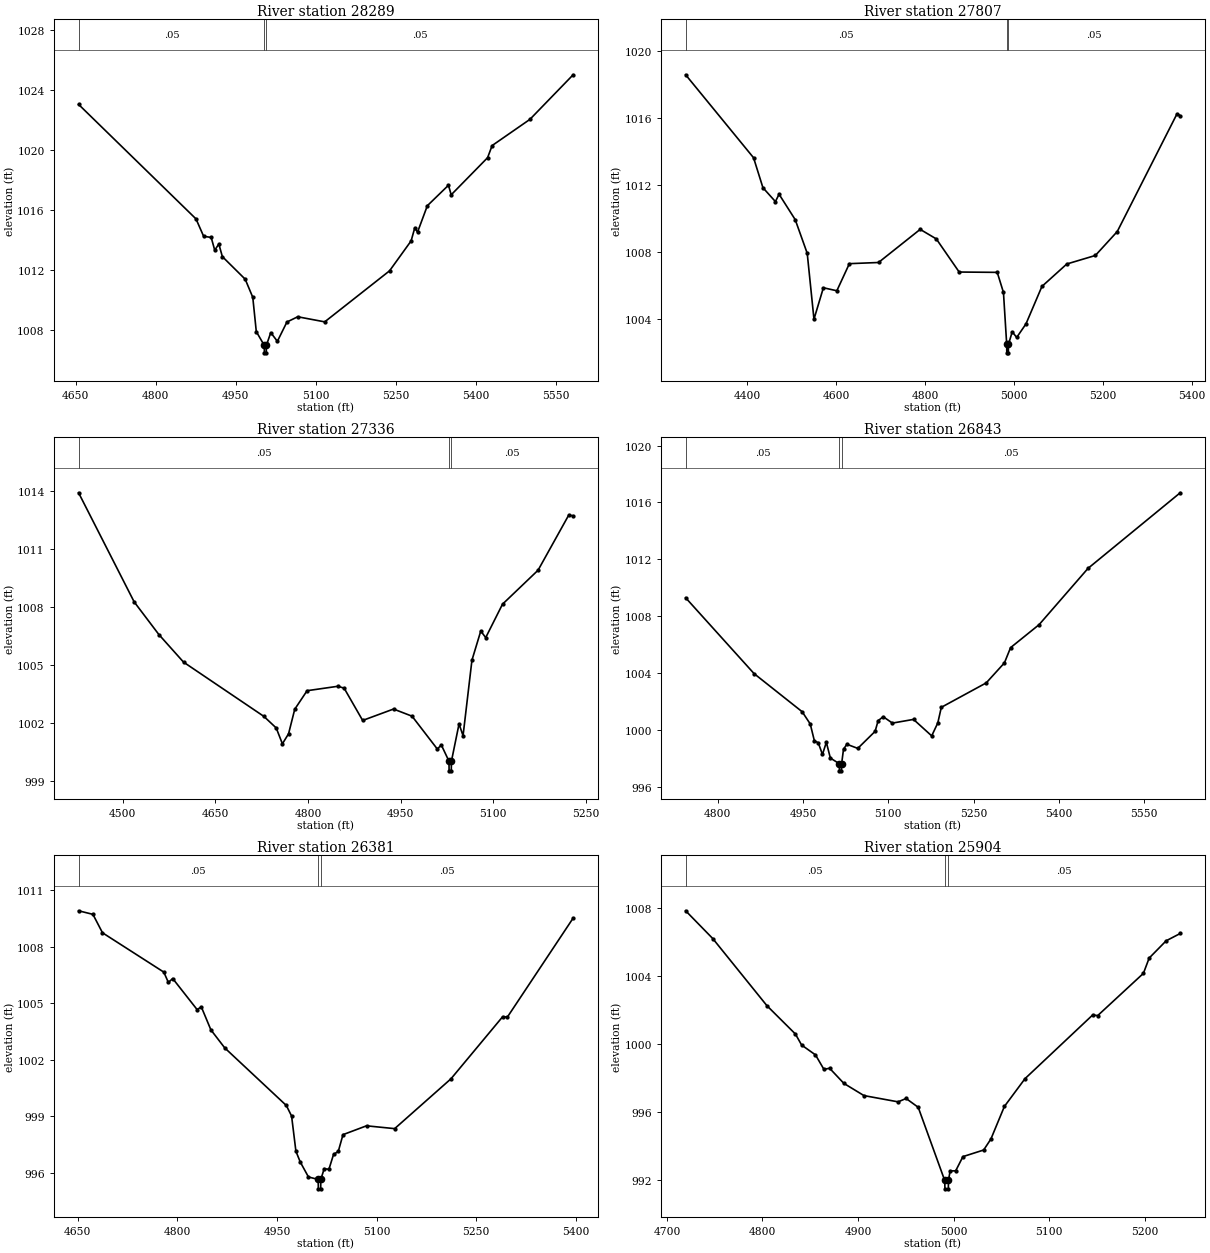
Type RM Length L Ch R = 1,28289,482,482,482
BEGIN DESCRIPTION:
PENNINGTON CREEK 51.0
END DESCRIPTION:
XS GIS Cut Line= 3
      2872805.68     10244503.10      2872581.25     10244242.00
      2872005.67     10244153.11
#Sta/Elev= 30
  4655.7 1023.06  4875.7 1015.41  4890.0 1014.25  4904.2 1014.17  4910.8 1013.32
  4918.5 1013.73  4925.1 1012.89  4967.9 1011.38  4982.1 1010.17  4988.7 1007.88
  5003.6 1006.96  5003.9 1006.46  5007.4 1006.46  5007.6 1006.96  5015.8 1007.81
  5028.2 1007.23  5046.1 1008.52  5066.3 1008.87  5116.9 1008.53  5238.4 1011.94
  5278.8 1013.94  5285.7 1014.82  5290.8 1014.52  5309.2 1016.29  5348.8 1017.66
  5353.9 1017.02  5422.1 1019.50  5430.6 1020.31  5501.4 1022.06  5582.4 1025.04
#Mann=3,-1,0
  4655.7    0.05       0  5003.6    0.03       0  5007.6    0.05       0
Bank Sta=5003.6,5007.6
Exp/Cntr=0.3,0.1

Type RM Length L Ch R = 1,27807,471,471,471
BEGIN DESCRIPTION:
PENNINGTON CREEK 50.0
END DESCRIPTION:
XS GIS Cut Line= 3
      2873155.69     10243403.11      2872534.00     10243803.00
      2872255.67     10244053.12
#Sta/Elev= 30
  4260.8 1018.58  4413.7 1013.62  4434.8 1011.83  4462.9 1011.00  4471.1 1011.44
  4507.5 1009.92  4534.5 1007.91  4549.7 1003.97  4570.9 1005.85  4601.2 1005.67
  4629.4 1007.29  4695.0 1007.36  4788.8 1009.34  4825.1 1008.77  4876.6 1006.79
  4962.3 1006.77  4976.3 1005.57  4983.6 1002.46  4983.8 1001.96  4987.3 1001.96
  4987.6 1002.46  4996.0 1003.22  5006.1 1002.88  5027.0 1003.69  5062.9 1005.93
  5118.9 1007.27  5183.2 1007.78  5232.5 1009.21  5367.1 1016.25  5374.2 1016.14
#Mann=3,-1,0
  4260.8    0.05       0  4983.6    0.03       0  4987.6    0.05       0
Bank Sta=4983.6,4987.6
Exp/Cntr=0.3,0.1

Type RM Length L Ch R = 1,27336,493,493,493
BEGIN DESCRIPTION:
PENNINGTON CREEK 49.0
END DESCRIPTION:
XS GIS Cut Line= 3
      2872905.72     10243403.11      2872334.25     10243409.00
      2872155.66     10243553.13
#Sta/Elev= 30
  4428.5 1013.92  4518.5 1008.27  4558.5 1006.58  4598.5 1005.15  4728.6 1002.34
  4748.6 1001.74  4758.6 1000.92  4768.6 1001.44  4778.6 1002.71  4798.6 1003.67
  4848.6 1003.90  4858.6 1003.80  4888.6 1002.13  4938.6 1002.72  4968.6 1002.35
  5009.5 1000.65  5016.0 1000.86  5028.4 1000.02  5028.6  999.52  5032.1  999.52
  5032.4 1000.02  5044.7 1001.95  5051.2 1001.34  5065.6 1005.25  5079.9 1006.76
  5087.9 1006.42  5115.1 1008.15  5172.7 1009.91  5222.3 1012.76  5229.5 1012.73
#Mann=3,-1,0
  4428.5    0.05       0  5028.4    0.05       0  5032.4    0.05       0
Bank Sta=5028.4,5032.4
Exp/Cntr=0.3,0.1

Type RM Length L Ch R = 1,26843,462,462,462
BEGIN DESCRIPTION:
PENNINGTON CREEK 48.0
END DESCRIPTION:
XS GIS Cut Line= 3
      2872505.65     10242903.15      2872331.00     10243091.00
      2871755.66     10243303.12
#Sta/Elev= 30
  4743.5 1009.29  4863.9 1003.95  4948.4 1001.27  4962.6 1000.41  4969.9  999.22
  4976.7  999.09  4984.1  998.26  4990.9  999.12  4998.0  998.01  5013.8  997.61
  5014.0  997.11  5017.5  997.11  5017.8  997.61  5021.1  998.63  5027.0  998.98
  5046.2  998.69  5076.7  999.89  5082.0 1000.64  5090.9 1000.92  5107.1 1000.47
  5144.2 1000.73  5176.2  999.57  5186.9 1000.48  5193.1 1001.58  5272.1 1003.30
  5304.1 1004.71  5314.9 1005.78  5365.1 1007.40  5451.1 1011.36  5613.2 1016.68
#Mann=3,-1,0
  4743.5    0.05       0  5013.8    0.03       0  5017.8    0.05       0
Bank Sta=5013.8,5017.8
Exp/Cntr=0.3,0.1

Type RM Length L Ch R = 1,26381,477,477,477
BEGIN DESCRIPTION:
PENNINGTON CREEK 47.0
END DESCRIPTION:
XS GIS Cut Line= 3
      2872255.71     10242553.08      2872037.25     10242825.00
      2871755.66     10243103.14
#Sta/Elev= 30
  4651.2 1009.92  4672.8 1009.73  4687.2 1008.75  4779.5 1006.66  4786.4 1006.11
  4792.9 1006.32  4829.6 1004.67  4836.0 1004.81  4850.4 1003.59  4871.3 1002.63
  4964.0  999.57  4971.9  999.01  4978.4  997.14  4984.9  996.57  4997.3  995.77
  5011.9  995.64  5012.2  995.14  5015.7  995.14  5015.9  995.64  5021.0  996.21
  5028.1  996.18  5035.1  996.97  5042.2  997.13  5049.3  998.02  5084.7  998.49
  5127.1  998.34  5211.9 1000.99  5289.7 1004.29  5296.8 1004.27  5395.8 1009.53
#Mann=3,-1,0
  4651.2    0.05       0  5011.9    0.03       0  5015.9    0.05       0
Bank Sta=5011.9,5015.9
Exp/Cntr=0.3,0.1

Type RM Length L Ch R = 1,25904,476,476,476
BEGIN DESCRIPTION:
PENNINGTON CREEK 46.0
END DESCRIPTION:
XS GIS Cut Line= 3
      2871755.66     10242503.15      2871596.50     10242734.00
      2871505.68     10242953.12
#Sta/Elev= 30
  4719.6 1007.86  4748.0 1006.22  4804.7 1002.26  4834.5 1000.59  4841.0  999.94
  4855.5  999.36  4864.3  998.51  4870.3  998.57  4885.2  997.68  4906.2  996.96
  4942.0  996.59  4950.3  996.79  4963.0  996.27  4990.7  991.96  4991.0  991.46
  4994.5  991.46  4994.7  991.96  4996.4  992.52  5002.2  992.52  5009.8  993.36
  5031.5  993.75  5039.1  994.40  5053.2  996.32  5074.8  997.96  5145.5 1001.71
  5150.9 1001.68  5198.7 1004.17  5204.7 1005.07  5222.5 1006.09  5237.2 1006.52
#Mann=3,-1,0
  4719.6    0.05       0  4990.7    0.03       0  4994.7    0.05       0
Bank Sta=4990.7,4994.7
Exp/Cntr=0.3,0.1