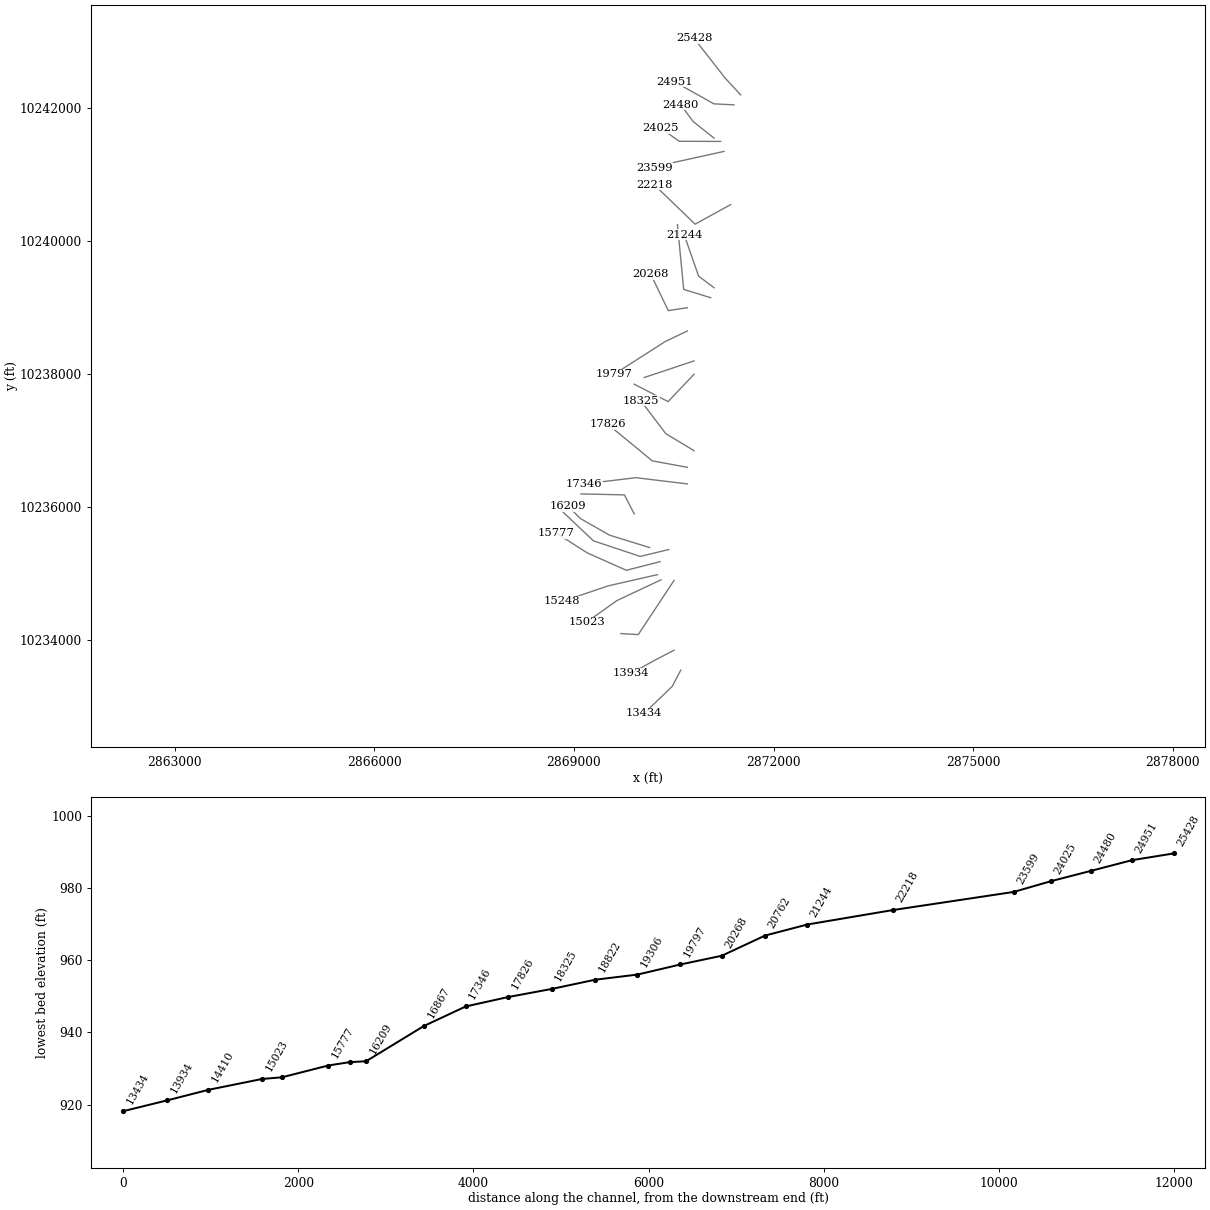
HEC-RAS study PENNINGTON CREEK.prj: PENNINGTON CREEK Base Level Engineering

--- PENNINGTON CREEK.g01 (geometry) --- (continued)

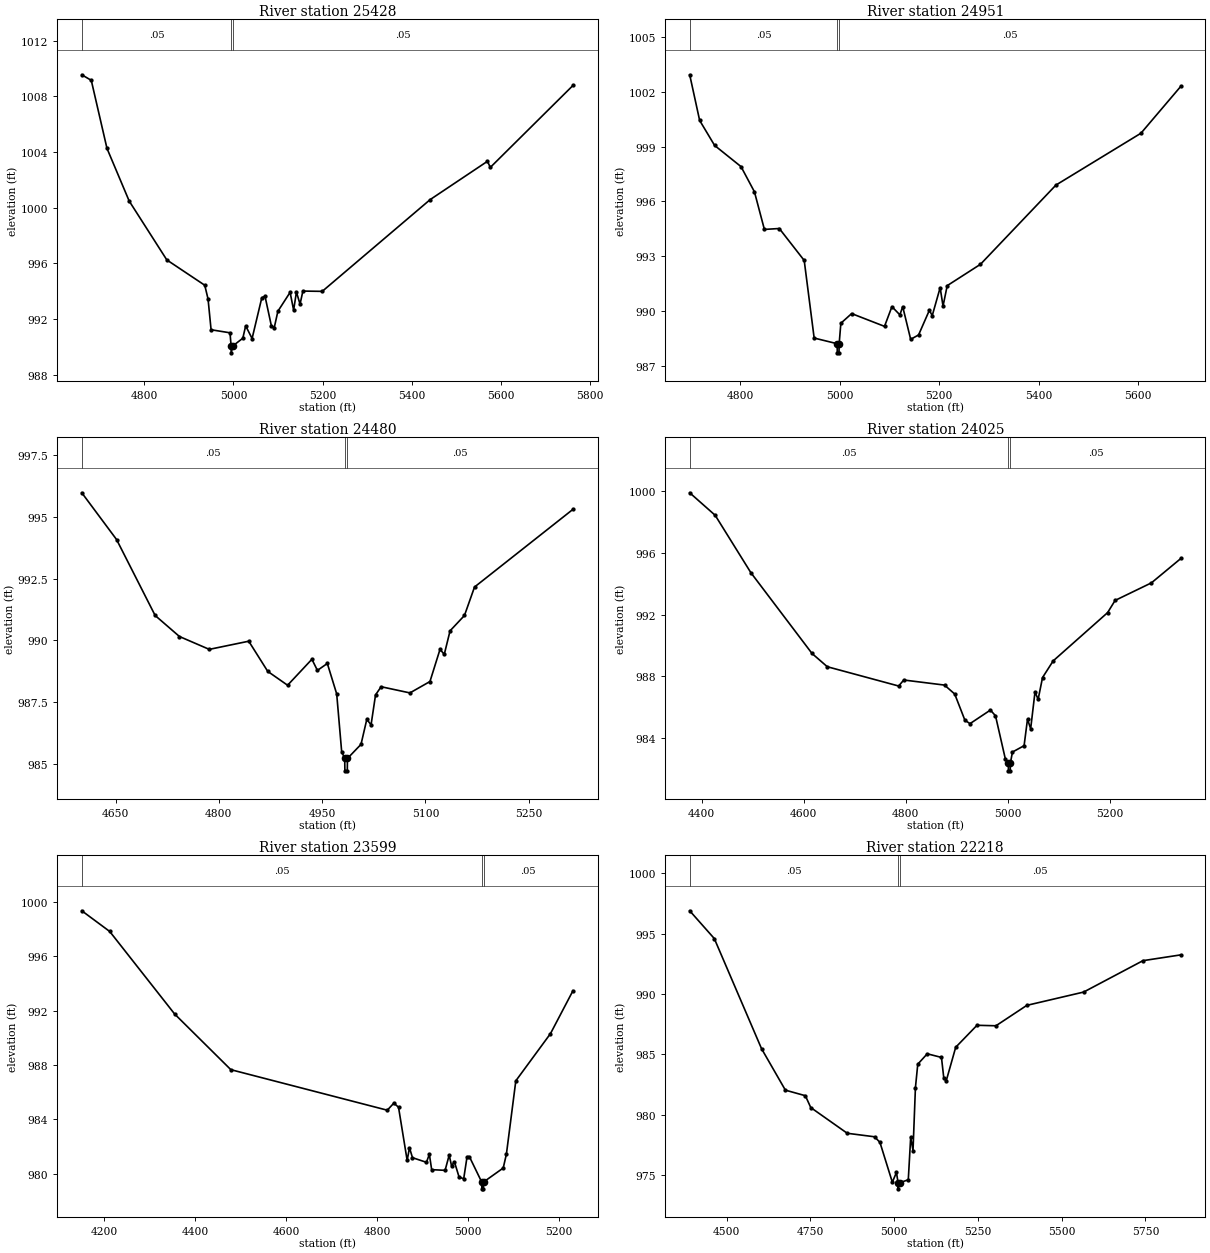
Type RM Length L Ch R = 1,25428,477,477,477
BEGIN DESCRIPTION:
PENNINGTON CREEK 45.0
END DESCRIPTION:
XS GIS Cut Line= 3
      2871505.71     10242203.08      2871274.75     10242453.00
      2870805.67     10243053.13
#Sta/Elev= 30
  4659.7 1009.56  4681.0 1009.16  4716.2 1004.27  4766.1 1000.48  4850.5  996.25
  4935.6  994.43  4943.0  993.44  4949.8  991.23  4992.3  991.01  4994.7  990.07
  4994.9  989.57  4998.7  990.07  5021.0  990.62  5027.4  991.51  5041.8  990.60
  5063.6  993.53  5070.8  993.64  5085.2  991.49  5091.6  991.39  5099.7  992.56
  5127.1  993.92  5135.0  992.64  5141.3  993.94  5149.4  993.07  5155.8  994.01
  5199.2  993.99  5441.5 1000.59  5569.9 1003.34  5576.3 1002.90  5761.7 1008.79
#Mann=3,-1,0
  4659.7    0.05       0  4994.7    0.05       0  4998.7    0.05       0
Bank Sta=4994.7,4998.7
Exp/Cntr=0.3,0.1

Type RM Length L Ch R = 1,24951,471,471,471
BEGIN DESCRIPTION:
PENNINGTON CREEK 44.0
END DESCRIPTION:
XS GIS Cut Line= 3
      2871405.68     10242053.11      2871104.25     10242068.00
      2870505.67     10242403.12
#Sta/Elev= 30
  4698.2 1002.93  4718.2 1000.43  4748.3  999.06  4801.4  997.90  4828.4  996.52
  4848.4  994.46  4878.4  994.51  4928.5  992.76  4948.5  988.51  4994.8  988.20
  4995.0  987.70  4998.5  987.70  4998.8  988.20  5002.2  989.32  5023.9  989.85
  5090.0  989.15  5104.9  990.23  5120.9  989.78  5126.6  990.23  5142.6  988.44
  5158.5  988.68  5180.2  990.03  5186.0  989.74  5201.9  991.27  5207.7  990.26
  5216.1  991.38  5283.0  992.55  5434.8  996.89  5605.8  999.73  5686.0 1002.30
#Mann=3,-1,0
  4698.2    0.05       0  4994.8    0.03       0  4998.8    0.05       0
Bank Sta=4994.8,4998.8
Exp/Cntr=0.3,0.1

Type RM Length L Ch R = 1,24480,455,455,455
BEGIN DESCRIPTION:
PENNINGTON CREEK 43.0
END DESCRIPTION:
XS GIS Cut Line= 3
      2871105.67     10241553.13      2870793.00     10241801.00
      2870605.67     10242053.13
#Sta/Elev= 30
  4601.0  995.97  4651.5  994.08  4707.5  991.01  4742.8  990.16  4786.1  989.64
  4843.4  989.97  4871.0  988.75  4899.8  988.19  4935.1  989.24  4943.1  988.79
  4957.5  989.07  4971.1  987.84  4978.3  985.51  4982.7  985.23  4983.0  984.73
  4986.5  984.73  4986.7  985.23  5006.4  985.80  5014.8  986.81  5021.0  986.59
  5027.5  987.80  5035.6  988.13  5077.4  987.88  5106.5  988.34  5121.1  989.64
  5127.3  989.44  5135.7  990.39  5156.6  991.01  5171.2  992.16  5314.1  995.30
#Mann=3,-1,0
  4601.0    0.05       0  4982.7    0.03       0  4986.7    0.05       0
Bank Sta=4982.7,4986.7
Exp/Cntr=0.3,0.1

Type RM Length L Ch R = 1,24025,426,426,426
BEGIN DESCRIPTION:
PENNINGTON CREEK 42.0
END DESCRIPTION:
XS GIS Cut Line= 3
      2871205.70     10241503.11      2870582.00     10241505.00
      2870305.68     10241703.11
#Sta/Elev= 30
  4376.3  999.91  4426.3  998.45  4496.3  994.73  4616.3  989.49  4646.3  988.63
  4786.3  987.38  4796.3  987.77  4876.3  987.44  4896.3  986.86  4916.3  985.16
  4926.3  984.94  4966.3  985.82  4976.3  985.45  4995.7  982.64  5001.5  982.38
  5001.7  981.88  5005.2  981.88  5005.5  982.38  5009.6  983.10  5032.4  983.51
  5039.1  985.23  5045.3  984.61  5053.8  986.99  5060.0  986.52  5068.6  987.93
  5089.5  989.01  5196.3  992.14  5211.0  992.93  5282.3  994.07  5340.0  995.65
#Mann=3,-1,0
  4376.3    0.05       0  5001.5    0.03       0  5005.5    0.05       0
Bank Sta=5001.5,5005.5
Exp/Cntr=0.3,0.1

Type RM Length L Ch R = 1,23599,1381,1381,1381
BEGIN DESCRIPTION:
PENNINGTON CREEK 41.0
END DESCRIPTION:
XS GIS Cut Line= 3
      2871255.68     10241353.11      2870426.25     10241170.00
      2870205.67     10241103.11
#Sta/Elev= 30
  4150.6  999.34  4212.0  997.82  4354.8  991.75  4478.3  987.66  4822.3  984.68
  4836.7  985.20  4847.0  984.90  4866.0  980.99  4871.1  981.92  4877.7  981.19
  4908.4  980.85  4914.8  981.44  4919.9  980.31  4949.4  980.26  4958.4  981.38
  4963.6  980.59  4969.9  980.89  4980.1  979.77  4990.3  979.64  4997.7  981.26
  5002.9  981.26  5029.9  979.40  5030.2  978.90  5033.7  978.90  5033.9  979.40
  5077.2  980.43  5084.2  981.45  5104.9  986.84  5181.1  990.31  5230.5  993.46
#Mann=3,-1,0
  4150.6    0.05       0  5029.9    0.03       0  5033.9    0.05       0
Bank Sta=5029.9,5033.9
Exp/Cntr=0.3,0.1

Type RM Length L Ch R = 1,22218,974,974,974
BEGIN DESCRIPTION:
PENNINGTON CREEK 40.0
END DESCRIPTION:
XS GIS Cut Line= 3
      2871355.69     10240553.11      2870821.50     10240259.00
      2870205.67     10240853.12
#Sta/Elev= 30
  4390.2  996.89  4463.6  994.59  4604.6  985.47  4675.7  982.04  4735.3  981.58
  4751.4  980.60  4860.3  978.47  4941.7  978.18  4957.8  977.72  4994.8  974.42
  5007.1  975.23  5012.0  974.37  5012.3  973.87  5016.2  974.37  5042.4  974.62
  5049.6  978.15  5056.5  977.04  5063.7  982.24  5070.7  984.19  5099.0  985.05
  5141.4  984.75  5148.4  983.03  5155.6  982.81  5183.9  985.59  5247.4  987.41
  5304.0  987.37  5396.1  989.06  5565.6  990.16  5742.6  992.76  5855.7  993.24
#Mann=3,-1,0
  4390.2    0.05       0  5012.0    0.05       0  5016.2    0.05       0
Bank Sta=5012,5016.2
Exp/Cntr=0.3,0.1

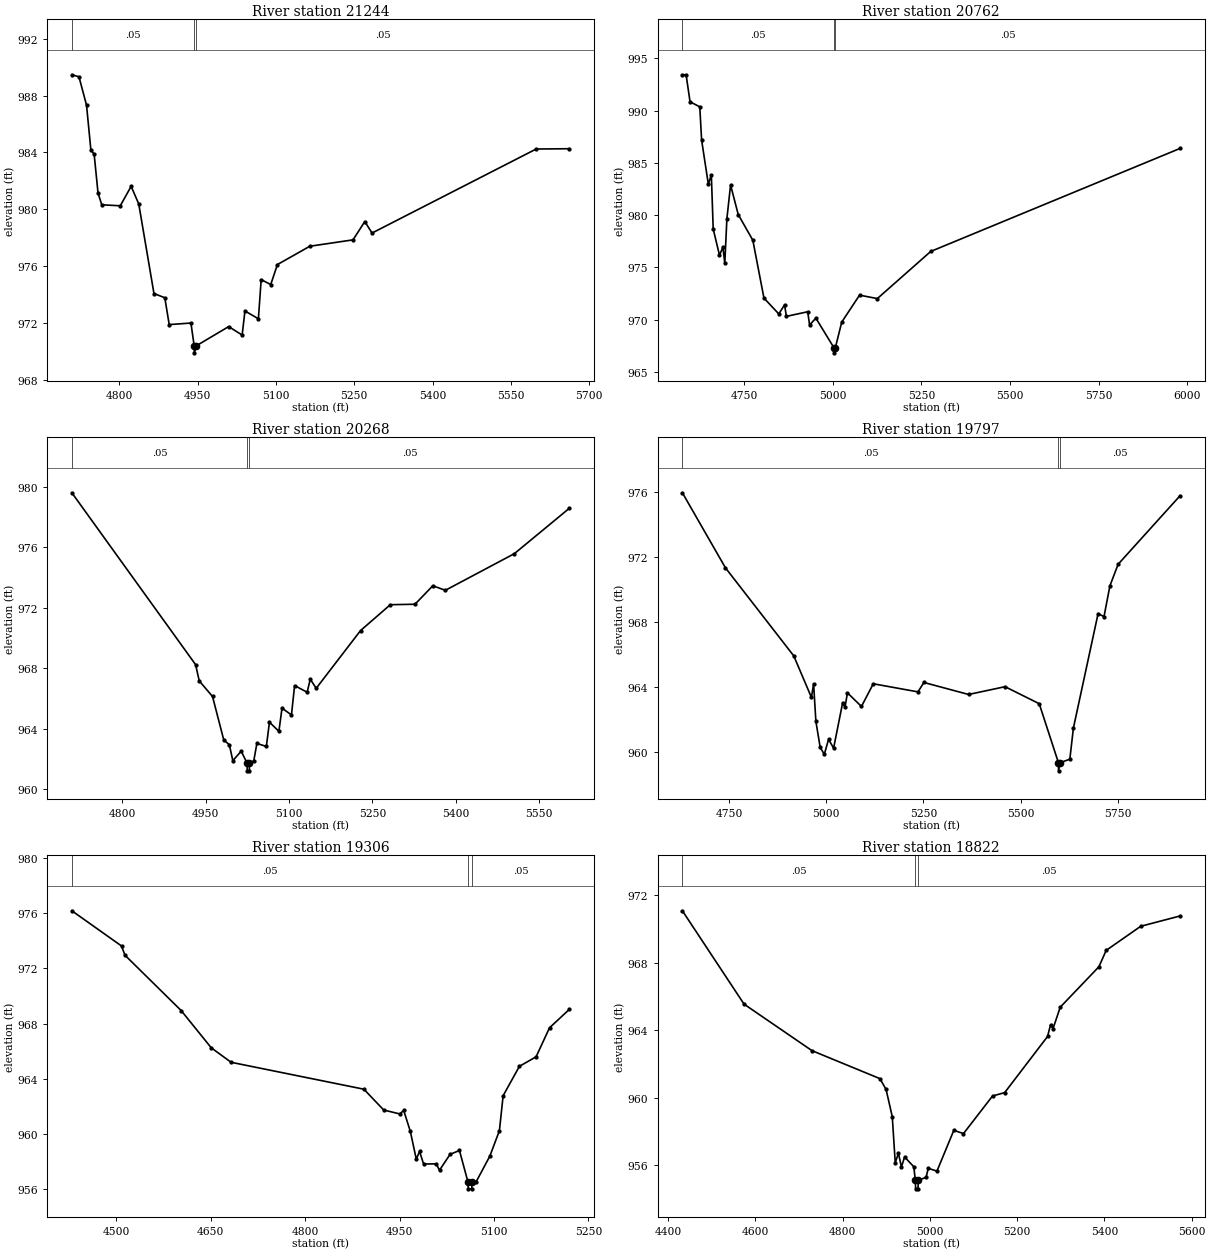
Type RM Length L Ch R = 1,21244,482,482,482
BEGIN DESCRIPTION:
PENNINGTON CREEK 39.0
END DESCRIPTION:
XS GIS Cut Line= 3
      2871105.70     10239303.10      2870873.50     10239478.00
      2870655.68     10240103.14
#Sta/Elev= 30
  4709.3  989.47  4722.9  989.33  4737.4  987.33  4745.7  984.18  4752.0  983.87
  4759.4  981.14  4766.6  980.31  4802.0  980.24  4822.8  981.61  4837.4  980.37
  4866.5  974.06  4887.3  973.76  4895.7  971.87  4937.3  971.98  4943.5  970.38
  4943.8  969.88  4947.8  970.38  5009.6  971.73  5035.4  971.13  5040.7  972.83
  5066.5  972.28  5071.8  975.04  5090.1  974.69  5102.9  976.10  5165.0  977.39
  5247.7  977.84  5270.2  979.13  5284.1  978.32  5598.4  984.24  5662.0  984.26
#Mann=3,-1,0
  4709.3    0.05       0  4943.5    0.03       0  4947.8    0.05       0
Bank Sta=4943.5,4947.8
Exp/Cntr=0.3,0.1

Type RM Length L Ch R = 1,20762,494,494,494
BEGIN DESCRIPTION:
PENNINGTON CREEK 38.0
END DESCRIPTION:
XS GIS Cut Line= 3
      2871055.71     10239153.10      2870650.00     10239278.00
      2870555.68     10240253.15
#Sta/Elev= 30
  4575.5  993.42  4586.0  993.42  4597.1  990.84  4624.6  990.35  4629.8  987.16
  4648.8  982.94  4657.2  983.86  4662.5  978.66  4680.2  976.16  4689.9  976.93
  4695.2  975.38  4701.1  979.65  4711.5  982.88  4733.1  980.05  4774.3  977.59
  4805.7  972.06  4847.6  970.54  4863.8  971.41  4869.1  970.31  4929.2  970.75
  4934.5  969.48  4952.2  970.14  5003.0  967.32  5003.3  966.82  5007.3  967.32
  5025.2  969.76  5075.5  972.34  5125.7  972.01  5276.4  976.52  5979.7  986.37
#Mann=3,-1,0
  4575.5    0.05       0  5003.0    0.05       0  5007.3    0.05       0
Bank Sta=5003,5007.3
Exp/Cntr=0.3,0.1

Type RM Length L Ch R = 1,20268,471,471,471
BEGIN DESCRIPTION:
PENNINGTON CREEK 37.0
END DESCRIPTION:
XS GIS Cut Line= 3
      2870705.73     10239003.12      2870418.50     10238959.00
      2870155.67     10239503.15
#Sta/Elev= 30
  4709.4  979.59  4932.0  968.24  4938.5  967.17  4962.4  966.14  4982.6  963.27
  4992.7  962.95  4998.9  961.90  5014.0  962.53  5024.6  961.73  5024.9  961.23
  5028.7  961.23  5028.9  961.73  5036.6  961.89  5042.2  963.04  5059.2  962.84
  5064.8  964.44  5081.8  963.84  5087.4  965.37  5104.4  964.92  5110.0  966.86
  5132.6  966.42  5138.2  967.28  5148.9  966.68  5228.6  970.49  5282.2  972.20
  5326.6  972.23  5358.6  973.45  5381.2  973.15  5505.3  975.57  5604.3  978.57
#Mann=3,-1,0
  4709.4    0.05       0  5024.6    0.03       0  5028.9    0.05       0
Bank Sta=5024.6,5028.9
Exp/Cntr=0.3,0.1

Type RM Length L Ch R = 1,19797,491,491,491
BEGIN DESCRIPTION:
PENNINGTON CREEK 36.0
END DESCRIPTION:
XS GIS Cut Line= 3
      2870705.68     10238653.11      2870371.75     10238494.00
      2869605.64     10238003.09
#Sta/Elev= 30
  4630.1  975.97  4740.9  971.34  4916.6  965.91  4962.0  963.35  4967.6  964.18
  4973.5  961.87  4984.6  960.26  4995.2  959.84  5006.1  960.76  5019.1  960.22
  5042.4  963.03  5048.4  962.75  5054.7  963.63  5090.7  962.79  5121.1  964.19
  5236.1  963.69  5251.3  964.27  5366.3  963.53  5460.1  964.01  5548.0  962.96
  5597.4  959.32  5597.7  958.82  5601.8  959.32  5626.7  959.54  5635.9  961.46
  5699.4  968.52  5714.6  968.33  5729.8  970.23  5750.9  971.56  5909.9  975.78
#Mann=3,-1,0
  4630.1    0.05       0  5597.4    0.03       0  5601.8    0.05       0
Bank Sta=5597.4,5601.8
Exp/Cntr=0.3,0.1

Type RM Length L Ch R = 1,19306,484,484,484
BEGIN DESCRIPTION:
PENNINGTON CREEK 35.0
END DESCRIPTION:
XS GIS Cut Line= 3
      2870805.70     10238203.12      2870264.50     10238022.00
      2870055.67     10237953.11
#Sta/Elev= 30
  4429.3  976.17  4508.2  973.62  4513.7  972.95  4603.0  968.94  4650.8  966.24
  4682.4  965.19  4893.3  963.24  4924.9  961.73  4950.3  961.45  4956.6  961.70
  4967.1  960.19  4976.6  958.17  4981.8  958.73  4988.2  957.82  5008.2  957.83
  5013.5  957.37  5030.3  958.52  5045.2  958.80  5058.7  956.52  5059.2  956.02
  5064.7  956.02  5065.2  956.52  5071.7  956.53  5093.5  958.39  5108.7  960.24
  5114.6  962.77  5140.5  964.90  5167.0  965.59  5188.3  967.69  5219.9  969.03
#Mann=3,-1,0
  4429.3    0.05       0  5058.7    0.05       0  5065.2    0.05       0
Bank Sta=5058.7,5065.2
Exp/Cntr=0.3,0.1

Type RM Length L Ch R = 1,18822,497,497,497
BEGIN DESCRIPTION:
PENNINGTON CREEK 34.0
END DESCRIPTION:
XS GIS Cut Line= 3
      2870805.67     10238003.10      2870415.50     10237591.00
      2869905.73     10237853.09
#Sta/Elev= 30
  4432.5  971.09  4573.9  965.55  4729.6  962.79  4885.3  961.13  4899.5  960.49
  4913.7  958.87  4920.5  956.14  4927.8  956.70  4934.7  955.89  4942.0  956.48
  4963.0  955.90  4966.7  955.09  4967.2  954.59  4972.7  954.59  4973.2  955.09
  4991.3  955.28  4996.2  955.81  5016.1  955.64  5054.8  958.06  5077.0  957.87
  5143.6  960.10  5171.4  960.30  5269.7  963.63  5276.6  964.33  5282.3  964.10
  5298.8  965.37  5387.5  967.77  5404.1  968.74  5483.3  970.17  5573.2  970.78
#Mann=3,-1,0
  4432.5    0.05       0  4966.7    0.03       0  4973.2    0.05       0
Bank Sta=4966.7,4973.2
Exp/Cntr=0.3,0.1

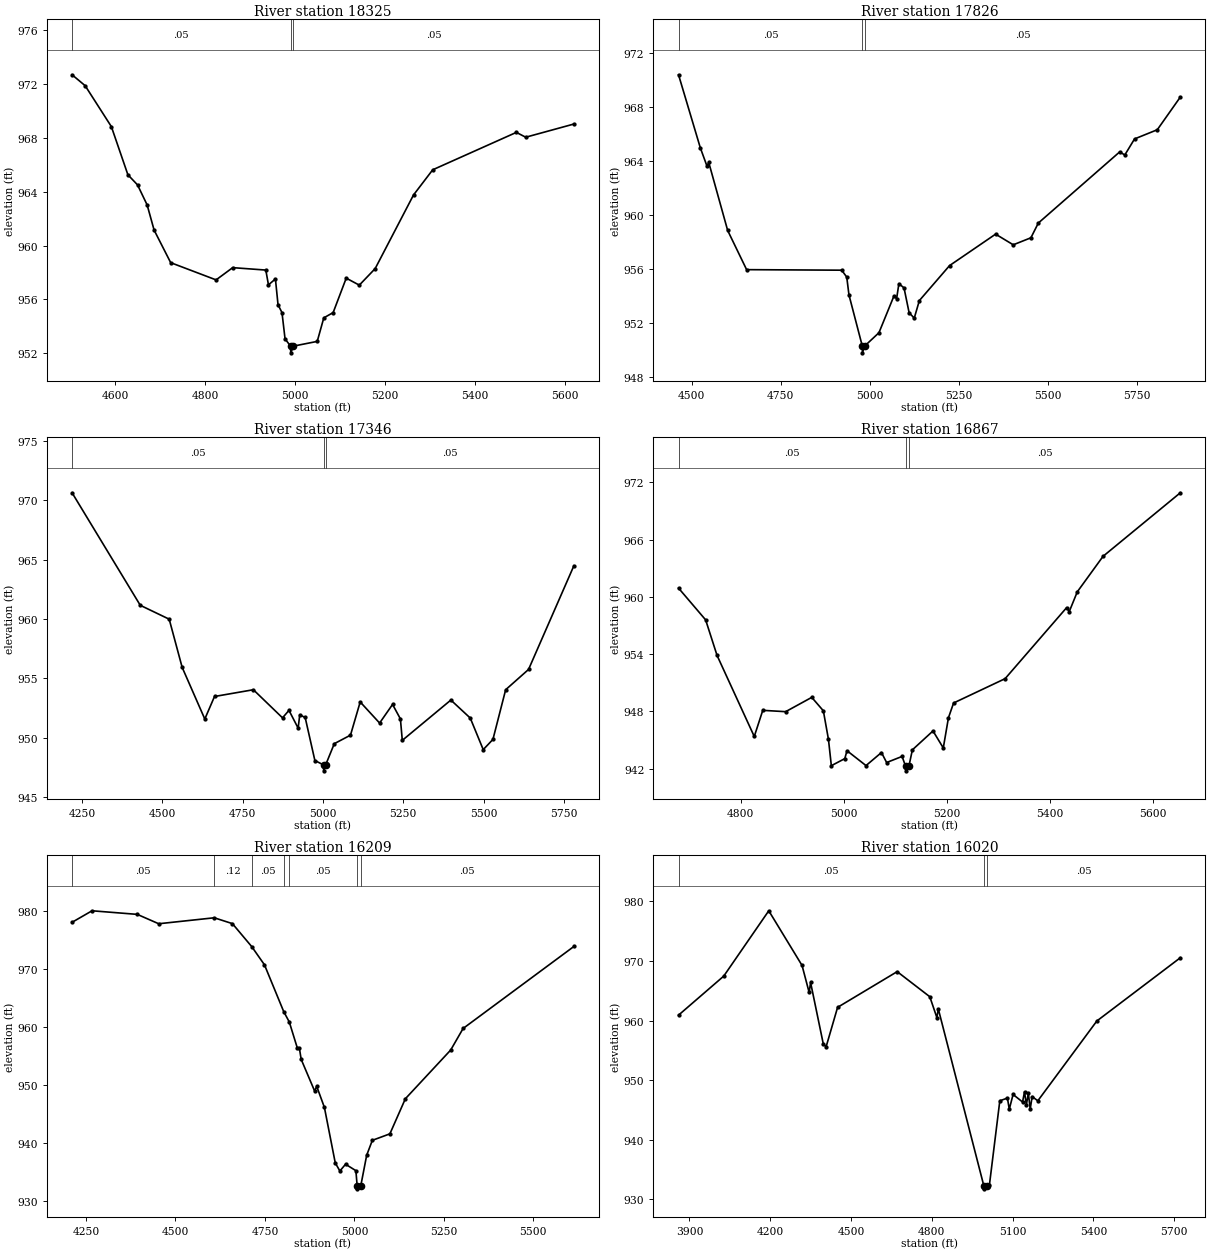
Type RM Length L Ch R = 1,18325,499,499,499
BEGIN DESCRIPTION:
PENNINGTON CREEK 33.0
END DESCRIPTION:
XS GIS Cut Line= 3
      2870805.67     10236853.12      2870381.00     10237109.00
      2870005.68     10237603.12
#Sta/Elev= 30
  4504.2  972.69  4533.3  971.88  4591.6  968.84  4628.4  965.26  4649.8  964.51
  4671.2  963.02  4686.7  961.15  4723.6  958.73  4824.6  957.45  4861.5  958.36
  4935.2  958.18  4941.1  957.08  4956.6  957.52  4962.4  955.60  4971.2  955.02
  4978.0  953.07  4990.2  952.53  4990.7  952.03  4996.7  952.53  5049.6  952.88
  5064.2  954.63  5085.0  955.02  5114.1  957.58  5143.2  957.06  5178.5  958.29
  5263.8  963.76  5306.5  965.63  5492.6  968.41  5513.4  968.05  5620.5  969.03
#Mann=3,-1,0
  4504.2    0.05       0  4990.2    0.05       0  4996.7    0.05       0
Bank Sta=4990.2,4996.7
Exp/Cntr=0.3,0.1

Type RM Length L Ch R = 1,17826,480,480,480
BEGIN DESCRIPTION:
PENNINGTON CREEK 32.0
END DESCRIPTION:
XS GIS Cut Line= 3
      2870705.68     10236603.11      2870178.00     10236700.00
      2869505.68     10237253.11
#Sta/Elev= 30
  4463.5  970.37  4524.5  964.97  4543.2  963.61  4548.2  963.88  4601.3  958.84
  4654.4  955.94  4921.0  955.90  4935.2  955.39  4941.4  954.07  4978.8  950.28
  4979.3  949.78  4985.3  950.28  5025.5  951.27  5067.7  954.00  5075.0  953.79
  5081.4  954.90  5095.8  954.59  5110.1  952.75  5124.5  952.35  5138.8  953.65
  5223.5  956.24  5352.6  958.57  5402.1  957.78  5451.6  958.30  5472.4  959.39
  5700.6  964.66  5714.9  964.43  5742.2  965.62  5806.0  966.30  5870.6  968.72
#Mann=3,-1,0
  4463.5    0.05       0  4978.8    0.05       0  4985.3    0.05       0
Bank Sta=4978.8,4985.3
Exp/Cntr=0.3,0.1

Type RM Length L Ch R = 1,17346,479,479,479
BEGIN DESCRIPTION:
PENNINGTON CREEK 31.0
END DESCRIPTION:
XS GIS Cut Line= 3
      2870705.68     10236353.11      2869930.75     10236447.00
      2869155.72     10236353.12
#Sta/Elev= 30
  4219.4  970.64  4431.6  961.15  4521.6  959.98  4561.9  955.92  4632.4  951.56
  4662.6  953.46  4783.5  954.03  4874.2  951.66  4894.3  952.29  4922.8  950.79
  4927.8  951.91  4944.7  951.69  4974.9  948.06  5001.8  947.69  5002.3  947.19
  5008.4  947.69  5035.3  949.48  5085.7  950.20  5115.9  953.00  5176.3  951.22
  5216.6  952.79  5241.0  951.57  5246.9  949.76  5398.0  953.16  5458.4  951.64
  5498.7  948.98  5528.9  949.84  5568.5  954.03  5639.7  955.74  5780.7  964.48
#Mann=3,-1,0
  4219.4    0.05       0  5001.8    0.05       0  5008.4    0.05       0
Bank Sta=5001.8,5008.4
Exp/Cntr=0.3,0.1

Type RM Length L Ch R = 1,16867,658,658,658
BEGIN DESCRIPTION:
PENNINGTON CREEK 30.0
END DESCRIPTION:
XS GIS Cut Line= 3
      2869905.68     10235903.13      2869759.25     10236188.00
      2869105.72     10236203.11
#Sta/Elev= 30
  4679.7  960.91  4732.3  957.58  4754.5  953.85  4826.7  945.36  4843.2  948.10
  4887.6  947.96  4938.3  949.46  4960.8  948.05  4970.7  945.06  4976.3  942.30
  5002.4  943.04  5006.7  943.87  5043.6  942.31  5073.6  943.68  5083.6  942.63
  5113.6  943.27  5120.3  942.26  5120.8  941.76  5126.9  942.26  5133.6  943.96
  5173.6  945.94  5193.6  944.16  5203.6  947.32  5213.6  948.87  5313.6  951.42
  5433.1  958.87  5438.1  958.45  5453.7  960.52  5503.7  964.24  5653.7  970.90
#Mann=3,-1,0
  4679.7    0.05       0  5120.3    0.05       0  5126.9    0.05       0
Bank Sta=5120.3,5126.9
Exp/Cntr=0.3,0.1

Type RM Length L Ch R = 1,16209,189,189,189
BEGIN DESCRIPTION:
Mapping XS 0f05c540
END DESCRIPTION:
XS GIS Cut Line= 4
      2870138.96     10235395.49      2869534.77     10235583.00
      2869097.27     10235833.00      2868909.76     10236020.52
#Sta/Elev= 30
  4211.4  978.06  4267.2  980.05  4393.5  979.43  4453.4  977.81  4608.6  978.84
  4659.3  977.83  4713.4  973.85  4748.8  970.72  4802.5  962.65  4818.2  960.84
  4840.9  956.29  4846.4  956.29  4851.5  954.37  4889.0  948.91  4894.7  949.74
  4916.3  946.08  4946.6  936.50  4959.5  935.10  4975.3  936.27  5004.2  935.16
  5007.8  932.52  5008.3  932.02  5017.8  932.52  5034.4  937.83  5050.2  940.40
  5099.2  941.52  5142.4  947.58  5269.1  956.00  5303.7  959.72  5613.1  973.88
#Mann=7,-1,0
  4211.4    0.05       0  4608.6    0.12       0  4713.4    0.05       0
  4802.5    0.12       0  4818.2    0.05       0  5007.8    0.03       0
  5017.8    0.05       0
Bank Sta=5007.8,5017.8
Exp/Cntr=0.3,0.1

Type RM Length L Ch R = 1,16020,243,243,243
BEGIN DESCRIPTION:
Mapping XS 6f7c82fb
END DESCRIPTION:
XS GIS Cut Line= 4
      2870426.29     10235367.07      2869996.64     10235262.91
      2869293.52     10235497.29      2868799.69     10235965.12
#Sta/Elev= 30
  3859.4  960.91  4027.3  967.46  4194.5  978.42  4318.1  969.25  4344.5  964.71
  4349.8  966.39  4397.4  955.99  4407.7  955.64  4450.1  962.22  4671.4  968.21
  4792.5  964.00  4818.8  960.50  4824.1  961.95  4993.2  932.27  4993.7  931.77
  5003.2  932.27  5013.8  932.37  5052.5  946.54  5080.8  947.00  5087.7  945.13
  5101.8  947.60  5137.0  946.34  5144.3  948.05  5151.2  945.85  5158.5  947.83
  5165.4  945.15  5172.6  947.25  5193.7  946.54  5412.9  959.93  5722.9  970.54
#Mann=3,-1,0
  3859.4    0.05       0  4993.2    0.03       0  5003.2    0.05       0
Bank Sta=4993.2,5003.2
Exp/Cntr=0.3,0.1

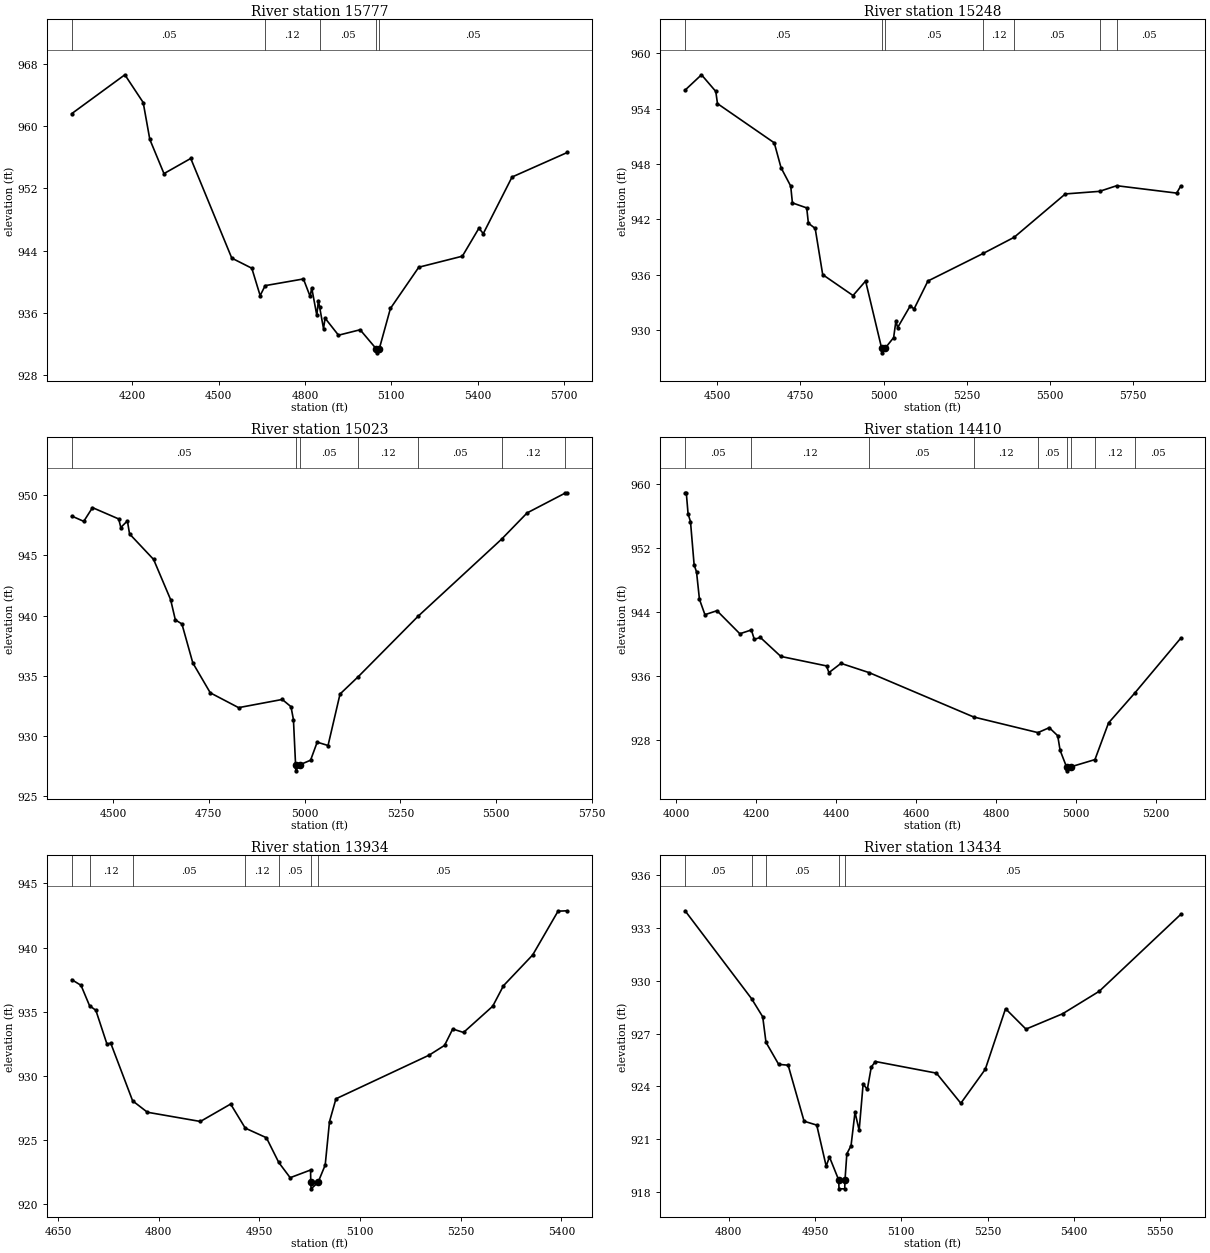
Type RM Length L Ch R = 1,15777,529,529,529
BEGIN DESCRIPTION:
Mapping XS 15e78047
END DESCRIPTION:
XS GIS Cut Line= 4
      2870296.08     10235184.78      2869788.31     10235054.58
      2869202.37     10235314.99      2868733.58     10235614.50
#Sta/Elev= 30
  3989.8  961.63  4174.3  966.63  4238.0  963.06  4261.0  958.31  4310.2  953.91
  4403.2  955.86  4545.8  943.03  4615.4  941.73  4644.3  938.21  4661.8  939.49
  4794.7  940.35  4818.0  938.10  4823.5  939.20  4841.2  935.67  4846.7  937.57
  4851.1  936.70  4864.5  933.96  4870.0  935.30  4916.5  933.11  4991.7  933.81
  5048.1  931.34  5048.6  930.84  5058.1  931.34  5096.9  936.55  5195.5  941.86
  5346.9  943.28  5404.4  946.88  5419.6  946.19  5519.5  953.47  5711.5  956.63
#Mann=5,-1,0
  3989.8    0.05       0  4661.8    0.12       0  4851.1    0.05       0
  5048.1    0.03       0  5058.1    0.05       0
Bank Sta=5048.1,5058.1
Exp/Cntr=0.3,0.1

Type RM Length L Ch R = 1,15248,225,225,225
BEGIN DESCRIPTION:
Mapping XS 49ec49b7
END DESCRIPTION:
XS GIS Cut Line= 3
      2870257.05     10234989.47      2869514.87     10234820.20
      2868824.72     10234585.81
#Sta/Elev= 30
  4403.0  955.99  4452.3  957.65  4495.3  955.85  4500.4  954.53  4671.1  950.29
  4691.6  947.59  4720.6  945.61  4725.7  943.79  4768.7  943.25  4773.8  941.59
  4794.2  941.03  4816.8  936.03  4908.0  933.77  4945.8  935.34  4994.0  928.07
  4994.5  927.57  5004.5  928.07  5030.1  929.22  5037.0  931.03  5042.1  930.30
  5080.0  932.65  5091.6  932.32  5133.2  935.34  5299.7  938.33  5392.5  940.07
  5546.4  944.76  5649.2  945.04  5700.9  945.65  5881.1  944.85  5893.1  945.59
#Mann=7,-1,0
  4403.0    0.05       0  4994.0    0.05       0  5004.5    0.05       0
  5299.7    0.12       0  5392.5    0.05       0  5649.2    0.12       0
  5700.9    0.05       0
Bank Sta=4994,5004.5
Exp/Cntr=0.3,0.1

Type RM Length L Ch R = 1,15023,613,613,613
BEGIN DESCRIPTION:
Mapping XS 32d18773
END DESCRIPTION:
XS GIS Cut Line= 3
      2870309.15     10234911.35      2869645.08     10234598.85
      2869189.98     10234273.78
#Sta/Elev= 30
  4392.2  948.25  4423.5  947.81  4446.3  948.95  4514.7  948.01  4520.2  947.30
  4537.4  947.85  4543.0  946.77  4605.8  944.65  4650.2  941.32  4662.5  939.64
  4679.7  939.30  4708.1  936.07  4753.7  933.59  4827.6  932.36  4941.5  933.04
  4964.3  932.44  4970.7  931.37  4976.3  927.62  4976.8  927.12  4986.9  927.62
  5015.4  928.00  5032.7  929.50  5061.0  929.22  5092.3  933.49  5140.2  934.94
  5296.0  939.94  5513.8  946.33  5580.5  948.51  5679.6  950.15  5685.4  950.18
#Mann=7,-1,0
  4392.2    0.05       0  4976.3    0.05       0  4986.9    0.05       0
  5140.2    0.12       0  5296.0    0.05       0  5513.8    0.12       0
  5679.6    0.05       0
Bank Sta=4976.3,4986.9
Exp/Cntr=0.3,0.1

Type RM Length L Ch R = 1,14410,476,476,476
BEGIN DESCRIPTION:
PENNINGTON CREEK 25.0
END DESCRIPTION:
XS GIS Cut Line= 3
      2870505.67     10234903.09      2869967.00     10234088.00
      2869705.64     10234103.11
#Sta/Elev= 30
  4023.0  958.96  4026.0  958.96  4030.5  956.31  4036.5  955.35  4045.6  949.93
  4051.6  949.04  4058.9  945.61  4072.6  943.68  4102.7  944.18  4159.9  941.29
  4188.7  941.77  4196.0  940.59  4211.1  940.83  4262.3  938.45  4376.6  937.26
  4382.6  936.42  4412.7  937.58  4483.6  936.41  4744.4  930.86  4905.1  928.90
  4933.4  929.52  4954.5  928.51  4960.5  926.68  4976.5  924.61  4977.0  924.11
  4987.2  924.61  5047.6  925.52  5081.5  930.11  5146.8  933.84  5261.8  940.72
#Mann=9,-1,0
  4023.0    0.05       0  4188.7    0.12       0  4483.6    0.05       0
  4744.4    0.12       0  4905.1    0.05       0  4976.5    0.05       0
  4987.2    0.05       0  5047.6    0.12       0  5146.8    0.05       0
Bank Sta=4976.5,4987.2
Exp/Cntr=0.3,0.1

Type RM Length L Ch R = 1,13934,500,500,500
BEGIN DESCRIPTION:
PENNINGTON CREEK 24.0
END DESCRIPTION:
XS GIS Cut Line= 3
      2870505.66     10233853.10      2870213.25     10233701.00
      2869855.66     10233503.10
#Sta/Elev= 30
  4670.4  937.49  4684.2  937.05  4696.9  935.46  4706.3  935.10  4722.8  932.47
  4728.5  932.53  4761.1  928.03  4783.1  927.14  4862.0  926.42  4907.1  927.78
  4928.9  925.90  4960.4  925.15  4978.8  923.22  4995.8  922.03  5026.2  922.63
  5026.5  921.66  5027.0  921.16  5037.3  921.66  5048.0  923.02  5054.4  926.41
  5064.0  928.19  5202.9  931.60  5225.8  932.36  5238.0  933.64  5254.1  933.37
  5297.6  935.42  5313.6  937.02  5357.1  939.42  5394.9  942.84  5408.7  942.87
#Mann=7,-1,0
  4670.4    0.05       0  4696.9    0.12       0  4761.1    0.05       0
  4928.9    0.12       0  4978.8    0.05       0  5026.5    0.03       0
  5037.3    0.05       0
Bank Sta=5026.5,5037.3
Exp/Cntr=0.3,0.1

Type RM Length L Ch R = 1,13434,492,492,492
BEGIN DESCRIPTION:
PENNINGTON CREEK 23.0
END DESCRIPTION:
XS GIS Cut Line= 3
      2870605.68     10233553.11      2870477.75     10233309.00
      2870055.66     10232903.09
#Sta/Elev= 30
  4724.4  933.97  4839.9  928.98  4859.3  927.95  4865.0  926.50  4887.0  925.25
  4903.5  925.20  4931.2  922.02  4953.2  921.80  4969.6  919.47  4975.3  919.99
  4991.4  918.68  4991.9  918.18  5001.8  918.18  5002.3  918.68  5005.5  920.17
  5012.8  920.63  5019.7  922.53  5026.9  921.50  5033.8  924.13  5041.1  923.83
  5048.0  925.10  5055.2  925.41  5161.2  924.75  5203.6  923.04  5246.1  924.97
  5281.3  928.41  5316.8  927.25  5380.4  928.12  5444.2  929.40  5585.6  933.76
#Mann=5,-1,0
  4724.4    0.05       0  4839.9    0.12       0  4865.0    0.05       0
  4991.4    0.05       0  5002.3    0.05       0
Bank Sta=4991.4,5002.3
Exp/Cntr=0.3,0.1