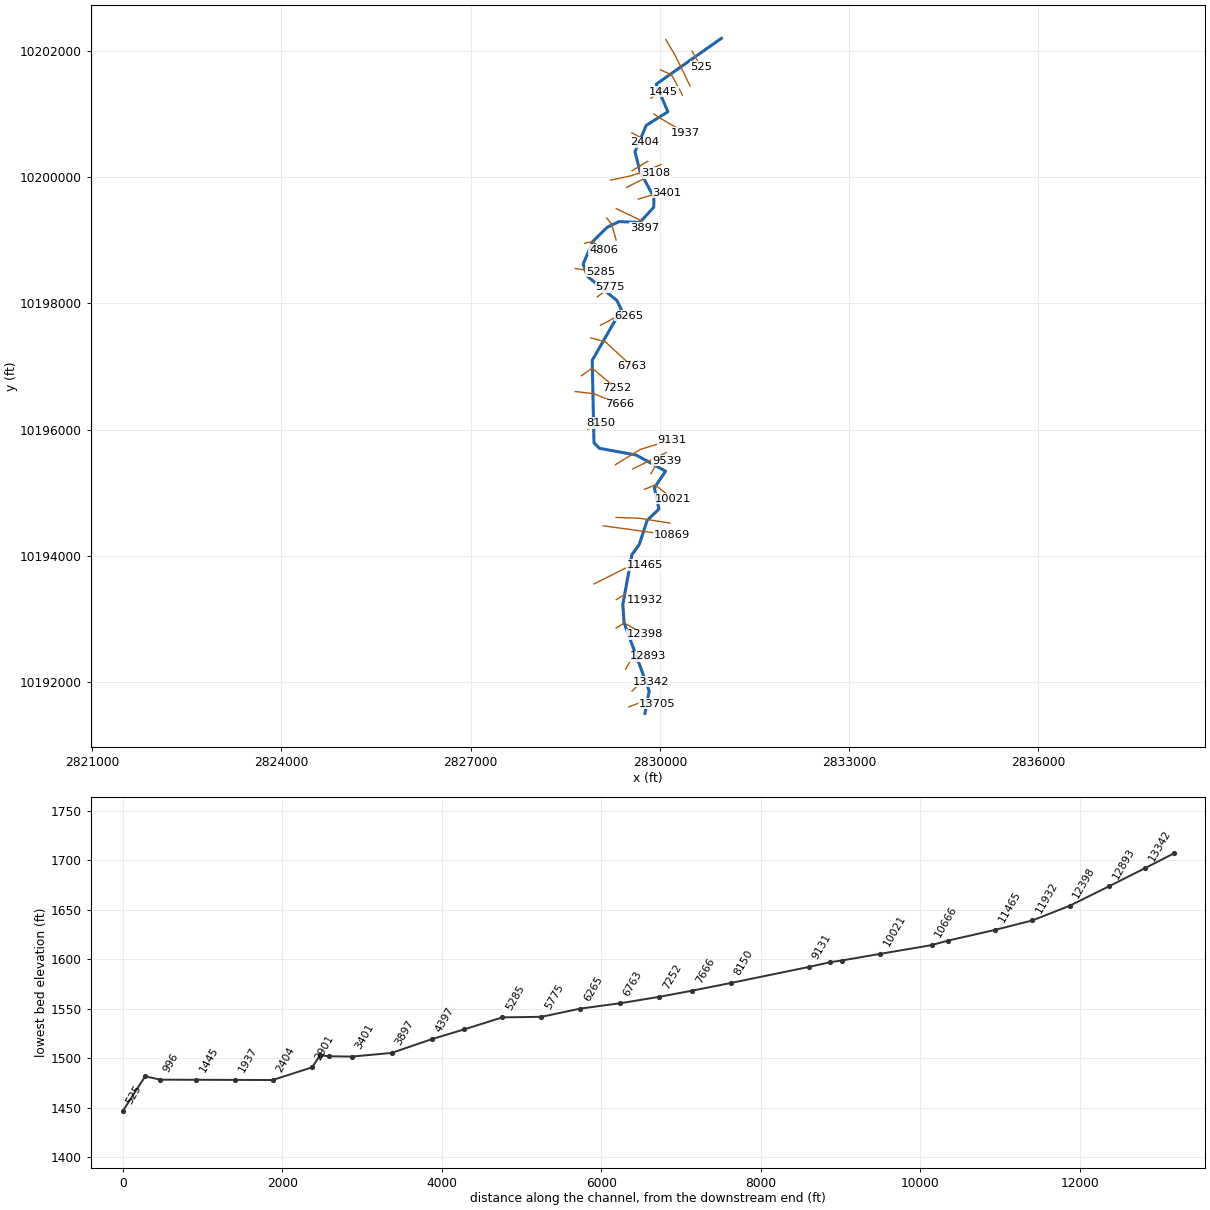
--- PYRAMID CREEK.prj (project) ---

Proj Title=PYRAMID CREEK Base Level Engineering
Current Plan=p01
Default Exp/Contr=0.3,0.1
English Units
Geom File=g01
Flow File=f01
Plan File=p01
BEGIN DESCRIPTION:
PYRAMID CREEK
END DESCRIPTION:

--- PYRAMID CREEK.p01 (plan) ---

Plan Title=Multiple Run
Short Identifier=Multiple
Geom File=g01
Flow File=f01
Subcritical Flow
K Sum by GR= 0
Std Step Tol= 0.01
Critical Tol= 0.01
Num of Std Step Trials= 20
Max Error Tol= 0.3
Flow Tol Ratio= 0.001
Split Flow NTrial= 30
Split Flow Tol= 0.02
Split Flow Ratio= 0.02
Log Output Level= 0
Friction Slope Method= 1
Unsteady Friction Slope Method= 2
Unsteady Bridges Friction Slope Method= 1
Parabolic Critical Depth
Global Vel Dist=  1 , 1 , 1
Global Log Level= 0
CheckData=True
Encroach Param= -1, 0, 0, 0
BEGIN DESCRIPTION:
Multiple Run
END DESCRIPTION:

--- PYRAMID CREEK.f01 (steady flow) ---

Flow Title=Multiple
Number of Profiles=7
Profile Names=10-year,25-year,50-year,1pct_min,100-year,1pct_plu,500-year
River Rch & RM= PYRAMID CREEK,Reach-1,13705
      86     167     264     138     417    1261    1121
River Rch & RM= PYRAMID CREEK,Reach-1,7666
     114     233     375     199     602    1817    1658
Boundary for River Rch & Prof#=PYRAMID CREEK,Reach-1,1
Up Type=0
Dn Type=3
Dn Slope=0.005
Boundary for River Rch & Prof#=PYRAMID CREEK,Reach-1,2
Up Type=0
Dn Type=3
Dn Slope=0.005
Boundary for River Rch & Prof#=PYRAMID CREEK,Reach-1,3
Up Type=0
Dn Type=3
Dn Slope=0.005
Boundary for River Rch & Prof#=PYRAMID CREEK,Reach-1,4
Up Type=0
Dn Type=3
Dn Slope=0.005
Boundary for River Rch & Prof#=PYRAMID CREEK,Reach-1,5
Up Type=0
Dn Type=3
Dn Slope=0.005
Boundary for River Rch & Prof#=PYRAMID CREEK,Reach-1,6
Up Type=0
Dn Type=3
Dn Slope=0.005
Boundary for River Rch & Prof#=PYRAMID CREEK,Reach-1,7
Up Type=0
Dn Type=3
Dn Slope=0.005

--- PYRAMID CREEK.g01 (geometry) ---

Geom Title=Existing Conditions

River Reach=PYRAMID CREEK,Reach-1
Reach XY= 30
      2829762.25     10191501.00      2829829.25     10191855.00
      2829431.75     10192934.00      2829411.00     10193225.00
      2829555.00     10194017.00      2829670.75     10194175.00
      2829796.25     10194559.00      2829983.75     10194741.00
      2829911.75     10195076.00      2830088.00     10195340.00
      2829624.00     10195596.00      2829041.25     10195703.00
      2828953.75     10195790.00      2828925.50     10197097.00
      2829388.00     10197903.00      2829316.25     10198047.00
      2828847.50     10198431.00      2828782.50     10198624.00
      2828933.25     10198980.00      2829162.00     10199206.00
      2829350.50     10199297.00      2829678.75     10199284.00
      2829900.50     10199522.00      2829903.75     10199684.00
      2829685.00     10200087.00      2829603.75     10200403.00
      2829781.75     10200822.00      2830125.25     10201038.00
      2829938.75     10201474.00      2830973.75     10202202.00

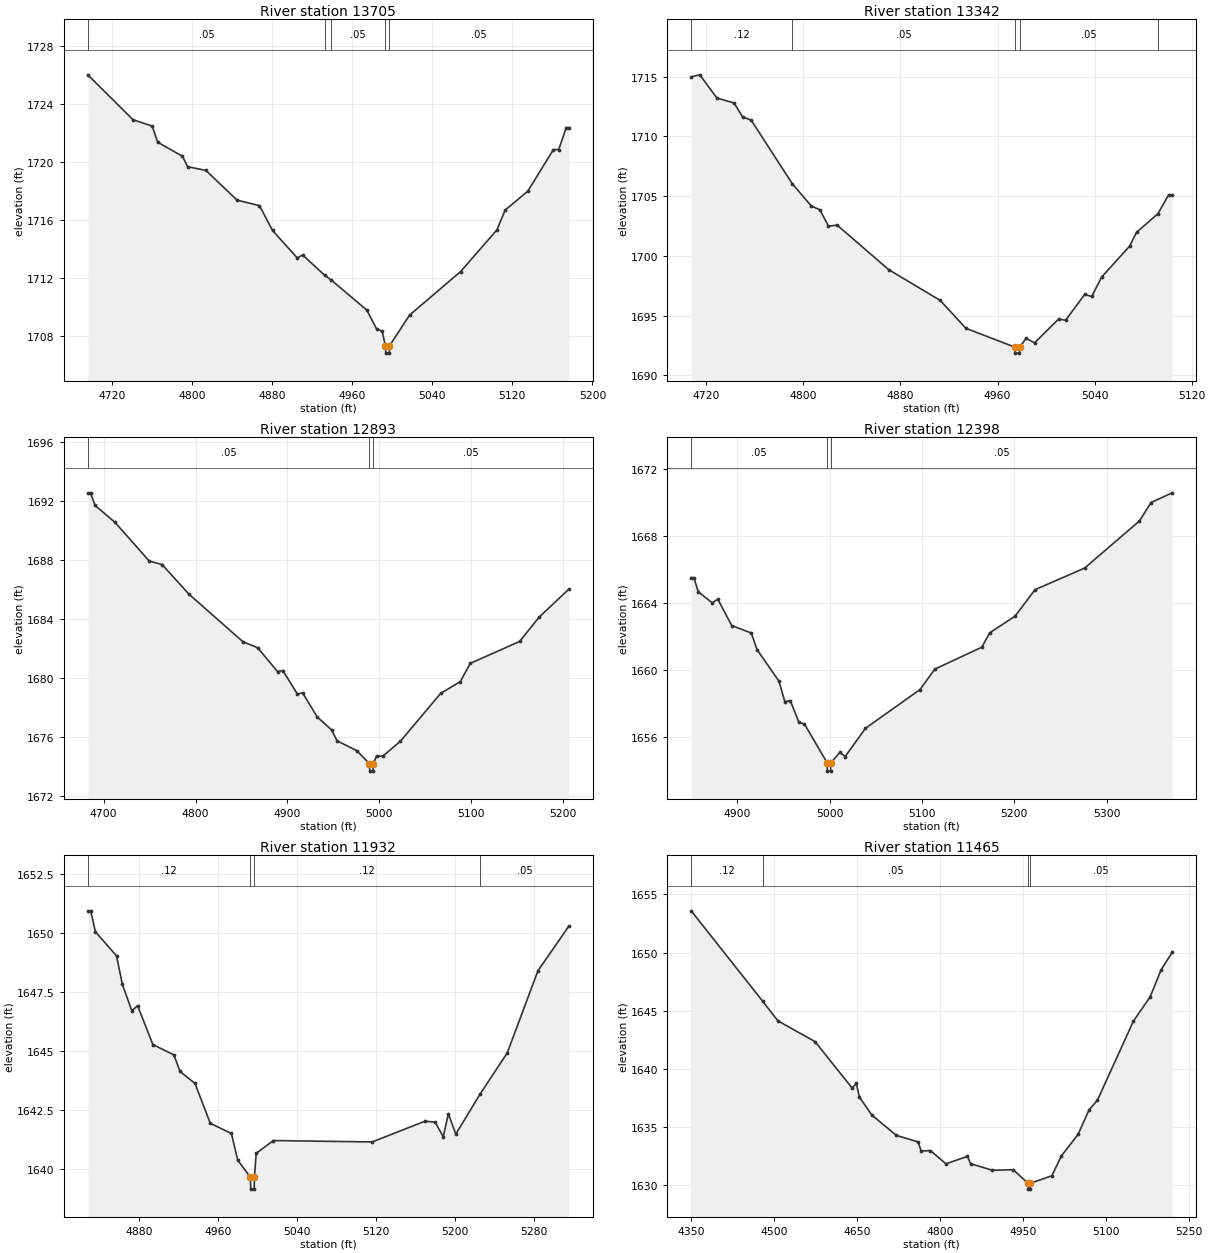
Type RM Length L Ch R = 1,13705,363,363,363
BEGIN DESCRIPTION:
PYRAMID CREEK 29.0
END DESCRIPTION:
XS GIS Cut Line= 3
      2829505.64     10191603.09      2829789.25     10191712.00
      2829955.64     10191653.13
#Sta/Elev= 30
  4696.2 1726.01  4741.3 1722.91  4760.5 1722.47  4765.9 1721.36  4790.6 1720.39
  4795.9 1719.67  4814.1 1719.41  4845.3 1717.36  4867.6 1716.98  4880.6 1715.27
  4905.3 1713.37  4910.7 1713.58  4932.9 1712.16  4939.0 1711.86  4974.8 1709.77
  4984.6 1708.46  4990.0 1708.32  4993.4 1707.30  4993.7 1706.80  4997.2 1706.80
  4997.4 1707.30  5017.4 1709.42  5068.4 1712.43  5104.6 1715.30  5112.9 1716.67
  5135.5 1717.98  5161.1 1720.85  5166.4 1720.85  5173.9 1722.37  5176.5 1722.37
#Mann=5,-1,0
  4696.2    0.05       0  4932.9    0.12       0  4939.0    0.05       0
  4993.4    0.05       0  4997.4    0.05       0
Bank Sta=4993.4,4997.4
Exp/Cntr=0.3,0.1

Type RM Length L Ch R = 1,13342,449,449,449
BEGIN DESCRIPTION:
PYRAMID CREEK 28.0
END DESCRIPTION:
XS GIS Cut Line= 3
      2829555.69     10191853.12      2829766.25     10192056.00
      2829855.68     10192003.11
#Sta/Elev= 30
  4707.6 1714.98  4714.7 1715.15  4728.8 1713.21  4743.0 1712.79  4749.9 1711.64
  4757.1 1711.35  4790.9 1706.04  4806.5 1704.18  4813.7 1703.85  4820.7 1702.49
  4827.9 1702.57  4870.3 1698.85  4912.8 1696.27  4933.9 1693.94  4974.3 1692.36
  4974.6 1691.86  4978.1 1691.86  4978.3 1692.36  4983.5 1693.10  4990.5 1692.72
  5010.3 1694.71  5016.1 1694.62  5031.8 1696.77  5037.6 1696.60  5045.8 1698.23
  5068.8 1700.81  5074.6 1701.98  5092.1 1703.52  5101.0 1705.11  5103.9 1705.11
#Mann=5,-1,0
  4707.6    0.12       0  4790.9    0.05       0  4974.3    0.05       0
  4978.3    0.05       0  5092.1    0.12       0
Bank Sta=4974.3,4978.3
Exp/Cntr=0.3,0.1

Type RM Length L Ch R = 1,12893,495,495,495
BEGIN DESCRIPTION:
PYRAMID CREEK 27.0
END DESCRIPTION:
XS GIS Cut Line= 3
      2829455.68     10192203.11      2829613.75     10192478.00
      2829805.66     10192403.12
#Sta/Elev= 30
  4682.9 1692.55  4685.8 1692.55  4690.8 1691.69  4712.4 1690.55  4749.7 1687.92
  4763.7 1687.68  4792.9 1685.67  4851.8 1682.43  4867.5 1682.04  4889.2 1680.42
  4894.9 1680.49  4910.7 1678.90  4916.5 1678.97  4932.3 1677.34  4948.1 1676.45
  4953.9 1675.72  4975.4 1675.05  4989.2 1674.16  4989.5 1673.66  4993.0 1673.66
  4993.2 1674.16  4996.9 1674.68  5003.7 1674.68  5022.7 1675.68  5066.5 1678.93
  5088.0 1679.74  5098.7 1680.97  5152.4 1682.46  5173.8 1684.12  5206.0 1686.01
#Mann=3,-1,0
  4682.9    0.05       0  4989.2    0.05       0  4993.2    0.05       0
Bank Sta=4989.2,4993.2
Exp/Cntr=0.3,0.1

Type RM Length L Ch R = 1,12398,466,466,466
BEGIN DESCRIPTION:
PYRAMID CREEK 26.0
END DESCRIPTION:
XS GIS Cut Line= 3
      2829305.67     10192853.10      2829431.75     10192934.00
      2829755.67     10192753.12
#Sta/Elev= 30
  4850.2 1665.52  4853.2 1665.52  4857.8 1664.68  4873.0 1664.01  4879.0 1664.23
  4894.2 1662.65  4915.3 1662.21  4921.5 1661.22  4945.3 1659.32  4951.6 1658.10
  4957.6 1658.16  4966.8 1656.87  4972.8 1656.77  4997.4 1654.45  4997.6 1653.95
  5001.1 1653.95  5001.4 1654.45  5011.2 1655.07  5016.9 1654.82  5038.9 1656.51
  5098.0 1658.83  5114.0 1660.05  5164.9 1661.36  5173.4 1662.22  5200.8 1663.21
  5222.5 1664.80  5276.2 1666.09  5335.6 1668.91  5348.1 1670.01  5371.0 1670.59
#Mann=3,-1,0
  4850.2    0.05       0  4997.4    0.05       0  5001.4    0.05       0
Bank Sta=4997.4,5001.4
Exp/Cntr=0.3,0.1

Type RM Length L Ch R = 1,11932,467,467,467
BEGIN DESCRIPTION:
PYRAMID CREEK 25.0
END DESCRIPTION:
XS GIS Cut Line= 3
      2829305.72     10193303.13      2829452.75     10193392.00
      2829755.68     10193303.11
#Sta/Elev= 30
  4828.2 1650.95  4831.1 1650.95  4835.9 1650.06  4857.3 1649.04  4863.2 1647.83
  4872.8 1646.71  4878.6 1646.93  4894.1 1645.28  4915.5 1644.84  4921.6 1644.14
  4936.8 1643.63  4952.3 1641.94  4973.7 1641.51  4980.1 1640.38  4993.0 1639.65
  4993.3 1639.15  4996.8 1639.15  4997.0 1639.65  4998.8 1640.67  5016.3 1641.21
  5116.4 1641.15  5169.8 1642.03  5180.2 1641.99  5188.4 1641.37  5193.6 1642.35
  5201.1 1641.48  5226.0 1643.20  5253.2 1644.92  5284.4 1648.41  5315.7 1650.30
#Mann=4,-1,0
  4828.2    0.12       0  4993.0    0.07       0  4997.0    0.12       0
  5226.0    0.05       0
Bank Sta=4993,4997
Exp/Cntr=0.3,0.1

Type RM Length L Ch R = 1,11465,596,596,596
BEGIN DESCRIPTION:
PYRAMID CREEK 24.0
END DESCRIPTION:
XS GIS Cut Line= 3
      2828955.67     10193553.11      2829536.00     10193845.00
      2829755.65     10193853.11
#Sta/Elev= 30
  4350.4 1653.59  4479.6 1645.81  4507.1 1644.12  4574.3 1642.33  4641.4 1638.33
  4648.9 1638.73  4654.5 1637.55  4676.9 1636.01  4721.5 1634.25  4760.6 1633.70
  4766.1 1632.91  4782.9 1632.95  4810.8 1631.81  4849.8 1632.45  4855.4 1631.82
  4894.5 1631.26  4932.5 1631.30  4959.4 1630.13  4959.7 1629.63  4963.2 1629.63
  4963.4 1630.13  5002.3 1630.78  5019.7 1632.50  5049.7 1634.34  5069.7 1636.47
  5084.5 1637.27  5149.8 1644.10  5179.8 1646.17  5199.8 1648.51  5219.8 1650.02
#Mann=4,-1,0
  4350.4    0.12       0  4479.6    0.05       0  4959.4    0.05       0
  4963.4    0.05       0
Bank Sta=4959.4,4963.4
Exp/Cntr=0.3,0.1

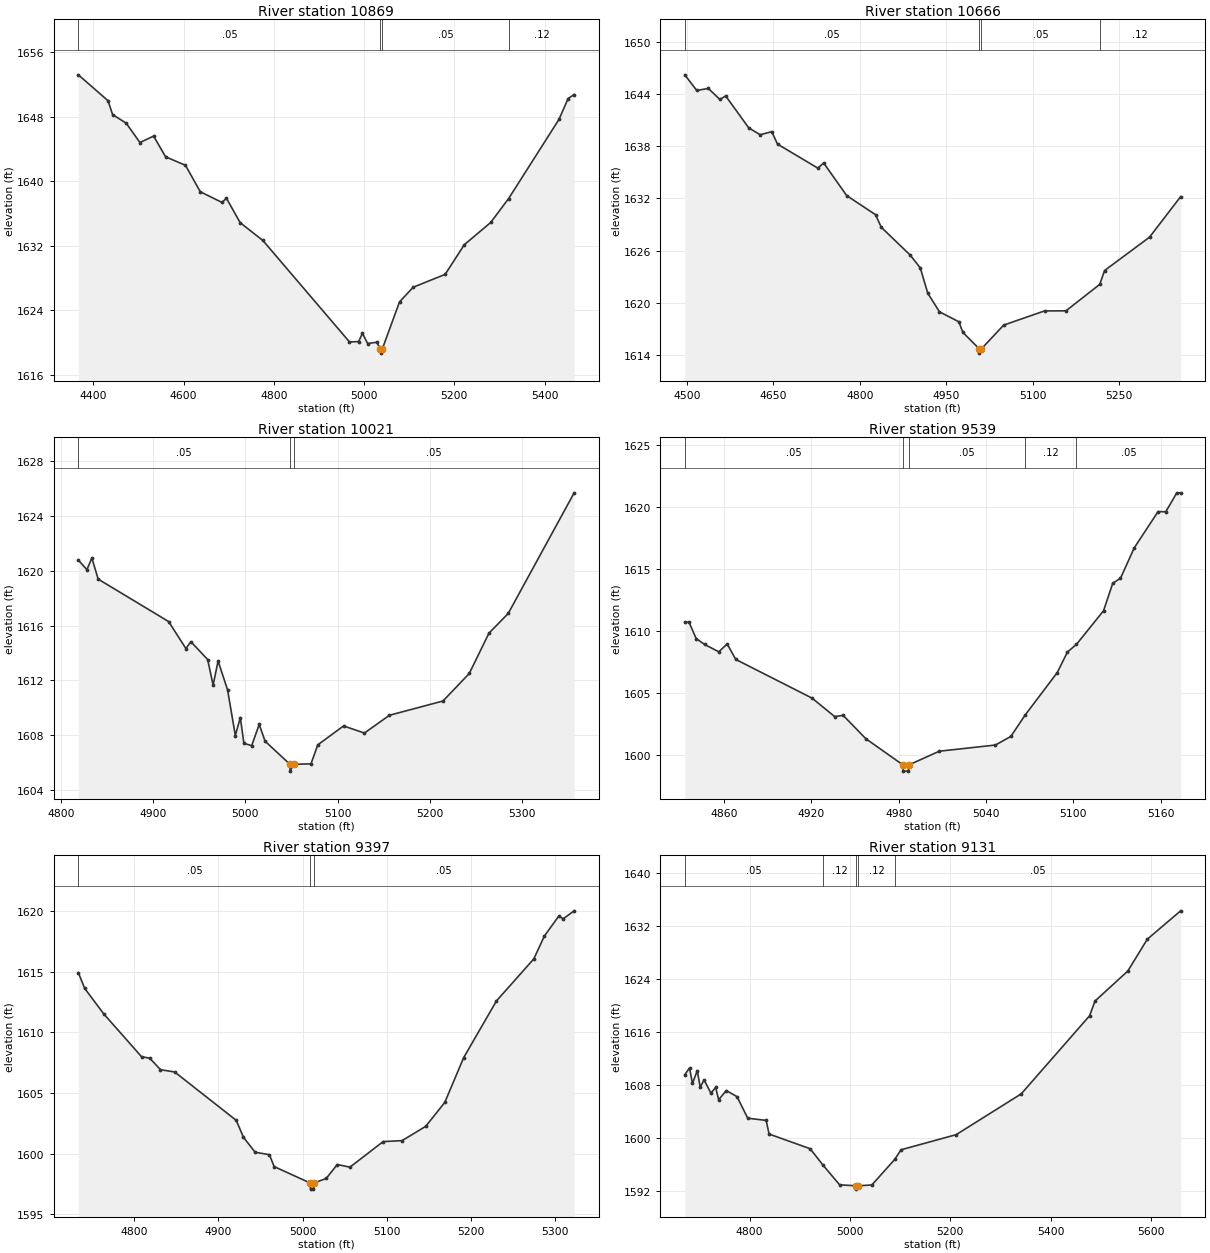
Type RM Length L Ch R = 1,10869,203,203,203
BEGIN DESCRIPTION:
Mapping XS 33b4e795
END DESCRIPTION:
XS GIS Cut Line= 2
      2829100.47     10194474.76      2830188.94     10194324.42
#Sta/Elev= 30
  4366.9 1653.19  4432.7 1649.98  4442.8 1648.27  4473.1 1647.19  4503.4 1644.80
  4533.7 1645.60  4560.3 1643.03  4604.3 1641.98  4637.2 1638.70  4685.1 1637.38
  4695.2 1637.89  4725.5 1634.87  4775.9 1632.66  4967.8 1620.09  4988.0 1620.13
  4996.6 1621.15  5008.1 1619.89  5028.3 1620.05  5036.4 1619.20  5036.7 1618.70
  5040.4 1619.20  5078.8 1625.06  5109.1 1626.87  5179.8 1628.46  5222.3 1632.14
  5280.7 1634.89  5320.5 1637.86  5432.1 1647.67  5452.3 1650.25  5465.7 1650.75
#Mann=4,-1,0
  4366.9    0.05       0  5036.4    0.05       0  5040.4    0.05       0
  5320.5    0.12       0
Bank Sta=5036.4,5040.4
Exp/Cntr=0.3,0.1

Type RM Length L Ch R = 1,10666,645,645,645
BEGIN DESCRIPTION:
Mapping XS 8091cdd1
END DESCRIPTION:
XS GIS Cut Line= 3
      2829304.86     10194607.07      2829671.76     10194595.04
      2830158.93     10194516.85
#Sta/Elev= 30
  4496.2 1646.19  4517.0 1644.39  4537.0 1644.63  4557.1 1643.36  4567.1 1643.77
  4607.1 1640.10  4627.1 1639.30  4647.1 1639.66  4657.1 1638.23  4727.1 1635.47
  4737.2 1636.06  4777.2 1632.31  4827.2 1630.12  4837.2 1628.67  4887.5 1625.47
  4904.9 1624.00  4917.9 1621.09  4938.2 1618.96  4971.9 1617.81  4978.7 1616.60
  5007.1 1614.71  5007.3 1614.21  5011.1 1614.71  5049.6 1617.43  5120.5 1619.06
  5157.7 1619.07  5216.3 1622.11  5224.7 1623.70  5302.8 1627.54  5356.7 1632.19
#Mann=4,-1,0
  4496.2    0.05       0  5007.1    0.05       0  5011.1    0.05       0
  5216.3    0.12       0
Bank Sta=5007.1,5011.1
Exp/Cntr=0.3,0.1

Type RM Length L Ch R = 1,10021,482,482,482
BEGIN DESCRIPTION:
PYRAMID CREEK 21.0
END DESCRIPTION:
XS GIS Cut Line= 3
      2829755.71     10195053.12      2829923.50     10195121.00
      2830205.67     10194903.12
#Sta/Elev= 30
  4819.0 1620.79  4828.3 1620.09  4833.7 1620.94  4840.5 1619.40  4916.9 1616.30
  4935.6 1614.33  4941.0 1614.83  4959.2 1613.53  4965.1 1611.66  4970.5 1613.42
  4980.8 1611.31  4989.2 1607.98  4994.6 1609.29  4998.5 1607.41  5006.9 1607.24
  5015.1 1608.79  5021.4 1607.57  5048.4 1605.88  5048.6 1605.38  5052.4 1605.88
  5071.2 1605.91  5078.6 1607.30  5106.5 1608.68  5129.1 1608.16  5156.3 1609.46
  5214.3 1610.50  5242.8 1612.51  5264.1 1615.45  5285.0 1616.89  5356.5 1625.70
#Mann=3,-1,0
  4819.0    0.05       0  5048.4    0.05       0  5052.4    0.05       0
Bank Sta=5048.4,5052.4
Exp/Cntr=0.3,0.1

Type RM Length L Ch R = 1,9539,142,142,142
BEGIN DESCRIPTION:
PYRAMID CREEK 20.0
END DESCRIPTION:
XS GIS Cut Line= 3
      2829855.69     10195303.12      2829941.75     10195446.00
      2830105.69     10195503.11
#Sta/Elev= 30
  4833.2 1610.70  4836.1 1610.70  4841.0 1609.38  4846.8 1608.90  4856.5 1608.31
  4862.3 1608.94  4868.2 1607.69  4920.6 1604.56  4936.1 1603.07  4941.9 1603.17
  4957.5 1601.28  4983.0 1599.16  4983.2 1598.66  4986.7 1598.66  4987.0 1599.16
  5007.9 1600.27  5046.5 1600.77  5057.1 1601.47  5066.7 1603.17  5088.9 1606.63
  5095.9 1608.29  5102.1 1608.91  5120.7 1611.63  5127.0 1613.85  5132.3 1614.25
  5141.8 1616.72  5158.1 1619.64  5163.4 1619.63  5171.0 1621.16  5173.6 1621.16
#Mann=5,-1,0
  4833.2    0.05       0  4983.0    0.05       0  4987.0    0.05       0
  5066.7    0.12       0  5102.1    0.05       0
Bank Sta=4983,4987
Exp/Cntr=0.3,0.1

Type RM Length L Ch R = 1,9397,266,266,266
BEGIN DESCRIPTION:
Mapping XS 6d2599d6
END DESCRIPTION:
XS GIS Cut Line= 3
      2829569.53     10195376.86      2829876.23     10195527.20
      2830098.73     10195635.45
#Sta/Elev= 30
  4733.5 1614.92  4741.1 1613.62  4763.6 1611.53  4808.6 1607.99  4818.3 1607.87
  4831.1 1606.92  4848.0 1606.73  4921.1 1602.74  4929.7 1601.34  4943.6 1600.11
  4960.5 1599.91  4966.1 1598.93  5009.1 1597.57  5009.3 1597.07  5012.8 1597.07
  5013.1 1597.57  5028.0 1597.95  5041.1 1599.10  5056.1 1598.88  5095.6 1600.99
  5118.1 1601.07  5146.2 1602.25  5168.8 1604.22  5191.3 1607.92  5230.2 1612.59
  5274.6 1616.06  5287.1 1617.94  5304.1 1619.57  5309.6 1619.37  5322.5 1620.02
#Mann=3,-1,0
  4733.5    0.05       0  5009.1    0.05       0  5013.1    0.05       0
Bank Sta=5009.1,5013.1
Exp/Cntr=0.3,0.1

Type RM Length L Ch R = 1,9131,981,981,981
BEGIN DESCRIPTION:
Mapping XS ad60bf63
END DESCRIPTION:
XS GIS Cut Line= 3
      2829292.91     10195443.03      2829683.78     10195683.57
      2830188.98     10195839.94
#Sta/Elev= 30
  4671.0 1609.50  4680.4 1610.51  4686.3 1608.19  4695.8 1610.11  4701.7 1607.63
  4709.5 1608.71  4723.0 1606.72  4732.5 1607.59  4738.4 1605.73  4753.8 1607.11
  4775.1 1606.18  4796.4 1602.93  4833.1 1602.60  4838.9 1600.54  4920.8 1598.32
  4946.5 1595.83  4979.5 1592.87  5012.8 1592.72  5013.0 1592.22  5016.8 1592.72
  5043.7 1592.85  5089.4 1596.72  5101.7 1598.16  5211.7 1600.45  5341.3 1606.61
  5477.4 1618.40  5488.3 1620.63  5553.5 1625.15  5592.5 1629.97  5658.8 1634.25
#Mann=5,-1,0
  4671.0    0.05       0  4946.5    0.12       0  5012.8    0.07       0
  5016.8    0.12       0  5089.4    0.05       0
Bank Sta=5012.8,5016.8
Exp/Cntr=0.3,0.1

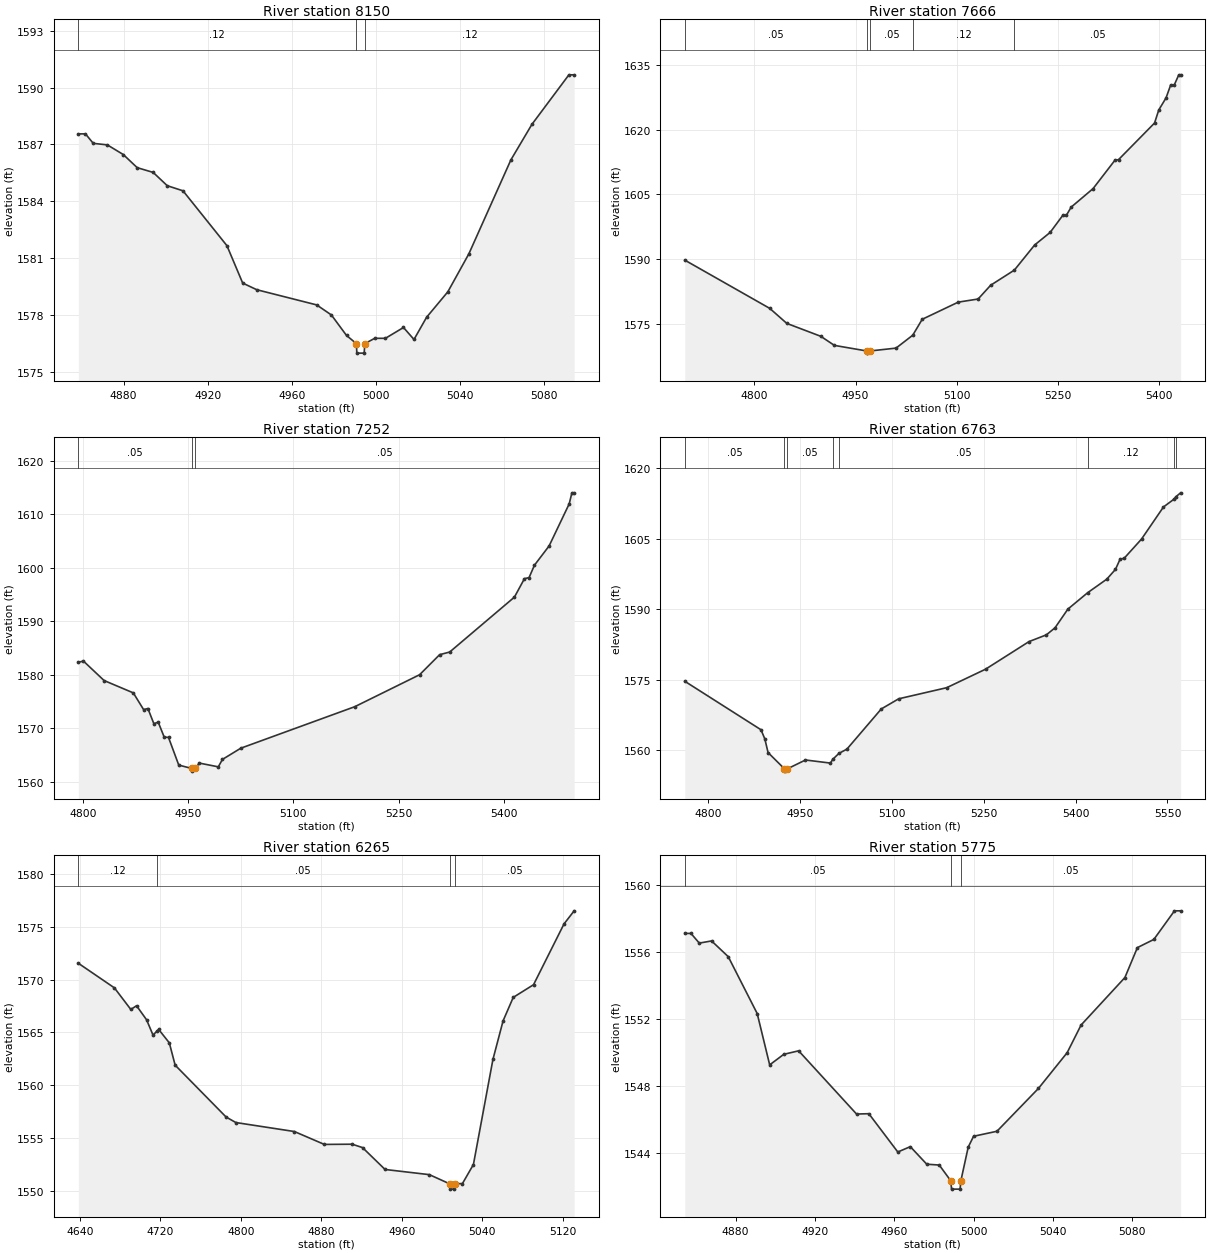
Type RM Length L Ch R = 1,8150,484,484,484
BEGIN DESCRIPTION:
PYRAMID CREEK 17.0
END DESCRIPTION:
XS GIS Cut Line= 3
      2828855.66     10196003.09      2828961.50     10196097.00
      2829055.70     10196103.11
#Sta/Elev= 30
  4858.5 1587.56  4861.9 1587.56  4865.6 1587.06  4872.3 1586.98  4879.9 1586.47
  4886.5 1585.78  4894.1 1585.53  4900.8 1584.83  4908.3 1584.56  4929.2 1581.67
  4936.7 1579.70  4943.4 1579.35  4971.9 1578.55  4978.9 1578.02  4986.1 1576.94
  4990.8 1576.51  4991.0 1576.01  4994.5 1576.01  4994.8 1576.51  4999.5 1576.79
  5004.6 1576.79  5013.2 1577.36  5018.2 1576.73  5024.2 1577.90  5034.3 1579.24
  5044.3 1581.24  5064.3 1586.19  5074.3 1588.06  5091.9 1590.67  5094.4 1590.67
#Mann=3,-1,0
  4858.5    0.12       0  4990.8    0.07       0  4994.8    0.12       0
Bank Sta=4990.8,4994.8
Exp/Cntr=0.3,0.1

Type RM Length L Ch R = 1,7666,414,414,414
BEGIN DESCRIPTION:
PYRAMID CREEK 16.0
END DESCRIPTION:
XS GIS Cut Line= 3
      2828655.66     10196603.11      2828956.50     10196567.00
      2829355.67     10196403.12
#Sta/Elev= 30
  4697.0 1589.78  4822.9 1578.61  4848.1 1575.14  4898.5 1572.15  4918.6 1570.05
  4966.5 1568.76  4966.9 1568.26  4971.4 1568.76  5009.9 1569.42  5034.7 1572.41
  5048.7 1576.09  5102.1 1580.06  5131.5 1580.78  5150.1 1583.97  5185.2 1587.47
  5215.3 1593.29  5238.2 1596.19  5256.8 1600.11  5262.2 1600.14  5269.4 1602.05
  5301.8 1606.33  5334.1 1612.88  5339.5 1613.03  5392.9 1621.51  5399.1 1624.52
  5409.9 1627.32  5416.8 1630.32  5422.2 1630.36  5428.8 1632.66  5431.5 1632.66
#Mann=5,-1,0
  4697.0    0.05       0  4966.5    0.05       0  4971.4    0.05       0
  5034.7    0.12       0  5185.2    0.05       0
Bank Sta=4966.5,4971.4
Exp/Cntr=0.3,0.1

Type RM Length L Ch R = 1,7252,489,489,489
BEGIN DESCRIPTION:
PYRAMID CREEK 15.0
END DESCRIPTION:
XS GIS Cut Line= 3
      2828755.69     10196853.11      2828922.50     10196975.00
      2829305.65     10196653.14
#Sta/Elev= 30
  4793.4 1582.35  4800.7 1582.57  4830.1 1578.94  4871.8 1576.63  4886.5 1573.50
  4892.6 1573.71  4901.1 1570.87  4907.3 1571.16  4915.8 1568.38  4922.0 1568.30
  4936.6 1563.14  4955.1 1562.51  4955.4 1562.01  4960.0 1562.51  4966.0 1563.51
  4993.0 1562.81  4998.9 1564.20  5025.0 1566.29  5187.6 1574.05  5280.0 1580.02
  5308.6 1583.77  5322.9 1584.26  5415.2 1594.52  5429.5 1597.97  5436.1 1598.17
  5443.8 1600.49  5464.7 1604.09  5493.3 1611.94  5497.2 1614.01  5500.4 1614.01
#Mann=3,-1,0
  4793.4    0.05       0  4955.1    0.05       0  4960.0    0.05       0
Bank Sta=4955.1,4960
Exp/Cntr=0.3,0.1

Type RM Length L Ch R = 1,6763,498,498,498
BEGIN DESCRIPTION:
PYRAMID CREEK 14.0
END DESCRIPTION:
XS GIS Cut Line= 3
      2828905.72     10197453.10      2829135.00     10197390.00
      2829555.65     10197003.14
#Sta/Elev= 30
  4762.2 1574.67  4886.6 1564.35  4892.9 1562.38  4898.1 1559.50  4924.8 1556.05
  4925.2 1555.55  4929.8 1556.05  4959.2 1557.92  5000.0 1557.26  5003.5 1558.03
  5013.7 1559.32  5026.8 1560.23  5082.9 1568.78  5111.3 1570.94  5189.6 1573.30
  5253.1 1577.24  5324.0 1583.11  5352.4 1584.55  5366.5 1586.05  5387.5 1590.03
  5419.9 1593.53  5451.0 1596.40  5465.2 1598.49  5472.6 1600.63  5479.4 1600.85
  5507.7 1604.93  5543.5 1611.76  5561.3 1613.48  5563.5 1613.91  5571.5 1614.77
#Mann=8,-1,0
  4762.2    0.05       0  4924.8    0.05       0  4929.8    0.05       0
  5003.5    0.12       0  5013.7    0.05       0  5419.9    0.12       0
  5561.3    0.05       0  5563.5    0.12       0
Bank Sta=4924.8,4929.8
Exp/Cntr=0.3,0.1

Type RM Length L Ch R = 1,6265,490,490,490
BEGIN DESCRIPTION:
PYRAMID CREEK 13.0
END DESCRIPTION:
XS GIS Cut Line= 3
      2829055.66     10197653.10      2829375.50     10197822.00
      2829505.64     10197803.12
#Sta/Elev= 30
  4638.3 1571.54  4674.2 1569.21  4690.5 1567.17  4696.2 1567.52  4706.2 1566.19
  4712.6 1564.74  4716.2 1565.09  4718.2 1565.28  4728.8 1564.01  4734.6 1561.90
  4785.3 1556.99  4795.0 1556.47  4853.2 1555.62  4883.0 1554.40  4910.7 1554.42
  4921.0 1554.10  4943.4 1552.03  4987.5 1551.54  5007.7 1550.67  5008.1 1550.17
  5012.4 1550.17  5012.8 1550.67  5020.4 1550.70  5031.3 1552.50  5050.7 1562.44
  5060.8 1566.09  5070.9 1568.31  5091.1 1569.51  5121.4 1575.26  5131.5 1576.50
#Mann=4,-1,0
  4638.3    0.12       0  4716.2    0.05       0  5007.7    0.05       0
  5012.8    0.05       0
Bank Sta=5007.7,5012.8
Exp/Cntr=0.3,0.1

Type RM Length L Ch R = 1,5775,490,490,490
BEGIN DESCRIPTION:
PYRAMID CREEK 12.0
END DESCRIPTION:
XS GIS Cut Line= 3
      2829005.67     10198103.10      2829122.50     10198190.00
      2829205.67     10198253.10
#Sta/Elev= 30
  4854.4 1557.13  4857.5 1557.13  4861.7 1556.55  4867.9 1556.68  4876.3 1555.74
  4890.9 1552.34  4897.2 1549.27  4904.3 1549.90  4911.8 1550.11  4941.0 1546.33
  4947.2 1546.35  4961.8 1544.06  4968.1 1544.38  4976.4 1543.33  4982.7 1543.28
  4988.5 1542.34  4988.9 1541.84  4993.2 1541.84  4993.6 1542.34  4997.3 1544.35
  5000.0 1545.00  5011.8 1545.30  5032.7 1547.86  5047.2 1550.00  5054.2 1551.65
  5076.3 1554.49  5082.6 1556.28  5090.9 1556.77  5101.3 1558.48  5104.4 1558.48
#Mann=3,-1,0
  4854.4    0.05       0  4988.5    0.05       0  4993.6    0.05       0
Bank Sta=4988.5,4993.6
Exp/Cntr=0.3,0.1

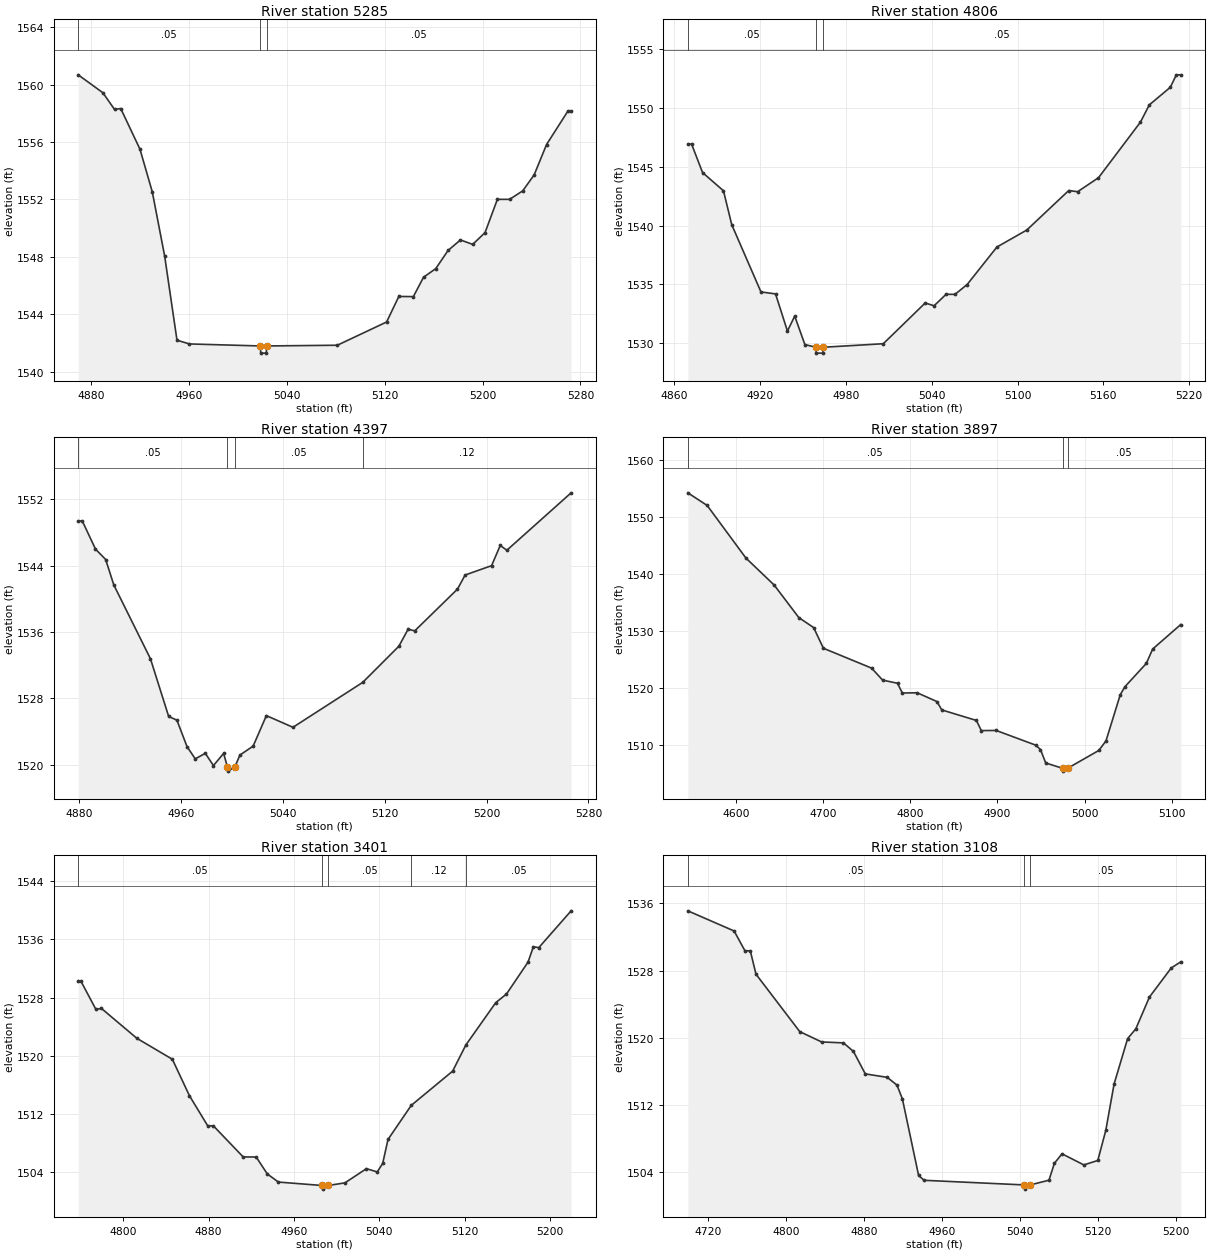
Type RM Length L Ch R = 1,5285,479,479,479
BEGIN DESCRIPTION:
PYRAMID CREEK 11.0
END DESCRIPTION:
XS GIS Cut Line= 3
      2828655.70     10198553.11      2828785.00     10198534.00
      2829055.64     10198503.12
#Sta/Elev= 30
  4869.3 1560.69  4889.5 1559.44  4899.0 1558.28  4904.1 1558.34  4919.8 1555.51
  4929.9 1552.53  4940.0 1548.06  4950.1 1542.19  4960.3 1541.93  5018.2 1541.79
  5018.6 1541.29  5023.1 1541.29  5023.5 1541.79  5081.2 1541.84  5121.5 1543.46
  5131.5 1545.24  5143.4 1545.23  5151.7 1546.58  5161.7 1547.18  5171.8 1548.45
  5181.9 1549.18  5191.9 1548.87  5202.0 1549.69  5212.1 1552.01  5222.1 1552.01
  5232.8 1552.60  5242.2 1553.72  5252.3 1555.83  5269.9 1558.18  5272.4 1558.18
#Mann=3,-1,0
  4869.3    0.05       0  5018.2    0.05       0  5023.5    0.05       0
Bank Sta=5018.2,5023.5
Exp/Cntr=0.3,0.1

Type RM Length L Ch R = 1,4806,409,409,409
BEGIN DESCRIPTION:
PYRAMID CREEK 10.0
END DESCRIPTION:
XS GIS Cut Line= 3
      2828805.65     10198953.11      2828933.25     10198980.00
      2829105.69     10198853.11
#Sta/Elev= 30
  4869.6 1546.94  4872.2 1546.94  4879.9 1544.51  4894.5 1542.96  4900.3 1540.07
  4920.7 1534.35  4930.9 1534.18  4939.2 1531.02  4944.3 1532.29  4951.4 1529.87
  4959.0 1529.64  4959.4 1529.14  4963.9 1529.14  4964.3 1529.64  5006.2 1529.94
  5035.5 1533.41  5041.7 1533.17  5050.1 1534.15  5056.3 1534.14  5064.8 1534.98
  5085.6 1538.17  5106.5 1539.62  5135.8 1542.98  5142.0 1542.88  5156.6 1544.07
  5185.9 1548.80  5192.1 1550.27  5206.8 1551.77  5211.0 1552.83  5214.1 1552.83
#Mann=3,-1,0
  4869.6    0.05       0  4959.0    0.05       0  4964.3    0.05       0
Bank Sta=4959,4964.3
Exp/Cntr=0.3,0.1

Type RM Length L Ch R = 1,4397,500,500,500
BEGIN DESCRIPTION:
PYRAMID CREEK 9.0
END DESCRIPTION:
XS GIS Cut Line= 3
      2829155.69     10199353.11      2829231.75     10199259.00
      2829305.70     10199003.07
#Sta/Elev= 30
  4879.0 1549.41  4882.2 1549.41  4892.6 1546.01  4900.6 1544.75  4907.0 1541.68
  4935.8 1532.77  4950.1 1525.81  4956.6 1525.36  4964.5 1522.18  4971.0 1520.69
  4978.9 1521.36  4985.3 1519.88  4993.3 1521.35  4996.3 1519.71  4996.8 1519.21
  5002.1 1519.71  5006.1 1521.15  5016.5 1522.23  5026.9 1525.91  5047.8 1524.50
  5102.6 1529.92  5131.0 1534.28  5138.3 1536.34  5143.5 1536.14  5177.1 1541.18
  5183.1 1542.88  5203.9 1544.01  5210.7 1546.45  5215.9 1545.87  5266.4 1552.80
#Mann=4,-1,0
  4879.0    0.05       0  4996.3    0.05       0  5002.1    0.05       0
  5102.6    0.12       0
Bank Sta=4996.3,5002.1
Exp/Cntr=0.3,0.1

Type RM Length L Ch R = 1,3897,496,496,496
BEGIN DESCRIPTION:
PYRAMID CREEK 8.0
END DESCRIPTION:
XS GIS Cut Line= 3
      2829305.67     10199503.12      2829715.75     10199306.00
      2829755.70     10199203.08
#Sta/Elev= 30
  4545.0 1554.29  4567.2 1552.07  4611.6 1542.84  4644.1 1538.08  4672.3 1532.38
  4689.3 1530.62  4700.5 1526.99  4755.8 1523.50  4768.4 1521.40  4785.5 1520.84
  4791.0 1519.13  4808.1 1519.17  4830.7 1517.63  4836.3 1516.16  4876.0 1514.31
  4881.6 1512.53  4898.7 1512.55  4943.9 1509.98  4949.5 1509.20  4955.5 1506.84
  4974.8 1505.91  4975.3 1505.41  4980.6 1505.91  5016.4 1509.04  5024.6 1510.71
  5041.0 1518.83  5046.3 1520.23  5070.9 1524.33  5078.2 1526.86  5110.4 1531.16
#Mann=3,-1,0
  4545.0    0.05       0  4974.8    0.05       0  4980.6    0.05       0
Bank Sta=4974.8,4980.6
Exp/Cntr=0.3,0.1

Type RM Length L Ch R = 1,3401,293,293,293
BEGIN DESCRIPTION:
PYRAMID CREEK 7.0
END DESCRIPTION:
XS GIS Cut Line= 3
      2829655.70     10199653.12      2829888.00     10199722.00
      2830105.69     10199753.11
#Sta/Elev= 30
  4757.7 1530.25  4760.3 1530.25  4774.3 1526.39  4779.5 1526.52  4812.7 1522.42
  4846.0 1519.54  4862.0 1514.54  4879.2 1510.39  4884.4 1510.41  4912.4 1506.13
  4924.6 1506.12  4935.0 1503.80  4945.4 1502.68  4986.4 1502.21  4986.8 1501.71
  4992.3 1502.21  5007.8 1502.57  5028.0 1504.52  5038.1 1504.07  5043.2 1505.23
  5048.2 1508.53  5070.0 1513.21  5108.8 1517.91  5121.2 1521.50  5149.2 1527.31
  5159.3 1528.50  5179.5 1532.88  5184.5 1534.98  5189.6 1534.87  5219.9 1539.92
#Mann=5,-1,0
  4757.7    0.05       0  4986.4    0.05       0  4992.3    0.05       0
  5070.0    0.12       0  5121.2    0.05       0
Bank Sta=4986.4,4992.3
Exp/Cntr=0.3,0.1

Type RM Length L Ch R = 1,3108,109,109,109
BEGIN DESCRIPTION:
Mapping XS 2c556cc6
END DESCRIPTION:
XS GIS Cut Line= 2
      2829473.30     10199839.20      2829924.31     10200067.72
#Sta/Elev= 30
  4699.6 1535.12  4747.1 1532.72  4758.1 1530.38  4763.7 1530.35  4769.5 1527.58
  4814.4 1520.75  4836.8 1519.52  4859.2 1519.41  4869.5 1518.39  4881.6 1515.72
  4904.1 1515.31  4914.1 1514.39  4919.7 1512.73  4936.3 1503.64  4941.9 1503.06
  5044.7 1502.51  5045.2 1502.01  5050.7 1502.51  5070.0 1503.07  5075.6 1505.09
  5083.4 1506.21  5105.8 1504.89  5120.1 1505.42  5128.3 1509.00  5136.8 1514.51
  5150.7 1519.92  5159.1 1521.08  5173.1 1524.87  5195.5 1528.33  5205.2 1529.05
#Mann=3,-1,0
  4699.6    0.05       0  5044.7    0.05       0  5050.7    0.05       0
Bank Sta=5044.7,5050.7
Exp/Cntr=0.3,0.1

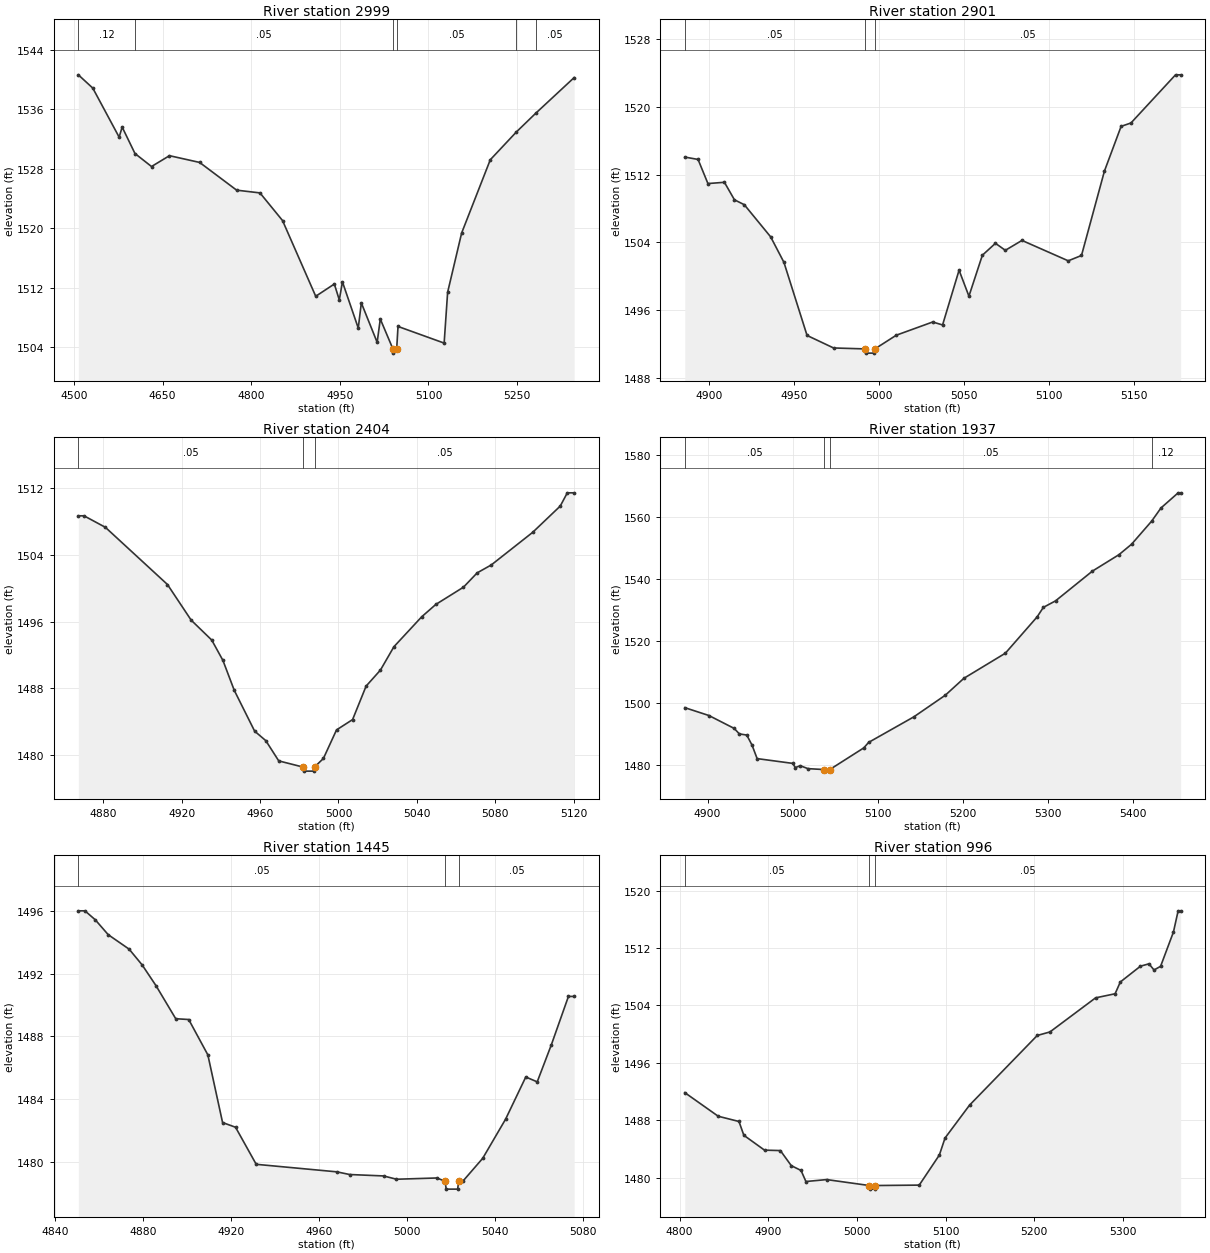
Type RM Length L Ch R = 1,2999,98,98,98
BEGIN DESCRIPTION:
Mapping XS 8c6507e3
END DESCRIPTION:
XS GIS Cut Line= 4
      2829214.69     10199953.47      2829527.42     10200019.62
      2829713.85     10200079.76      2830014.55     10200200.04
#Sta/Elev= 30
  4507.2 1540.64  4531.7 1538.85  4576.3 1532.25  4581.4 1533.61  4603.1 1530.05
  4631.1 1528.30  4661.5 1529.76  4712.6 1528.85  4775.2 1525.12  4814.7 1524.75
  4852.9 1521.03  4909.1 1510.84  4940.6 1512.49  4949.0 1510.35  4954.3 1512.78
  4981.1 1506.56  4986.3 1509.95  5013.1 1504.64  5018.4 1507.78  5040.1 1503.69
  5040.6 1503.19  5046.1 1503.69  5048.4 1506.78  5126.5 1504.54  5132.4 1511.38
  5156.1 1519.35  5204.6 1529.21  5248.9 1532.96  5281.3 1535.45  5346.6 1540.27
#Mann=6,-1,0
  4507.2    0.12       0  4603.1    0.05       0  5040.1    0.05       0
  5046.1    0.05       0  5248.9    0.12       0  5281.3    0.05       0
Bank Sta=5040.1,5046.1
Exp/Cntr=0.3,0.1

Type RM Length L Ch R = 1,2901,497,497,497
BEGIN DESCRIPTION:
PYRAMID CREEK 6.0
END DESCRIPTION:
XS GIS Cut Line= 3
      2829555.67     10200103.11      2829653.75     10200162.00
      2829805.72     10200253.13
#Sta/Elev= 30
  4885.6 1514.06  4893.4 1513.78  4899.2 1510.93  4908.9 1511.08  4914.8 1509.01
  4920.6 1508.43  4936.1 1504.63  4943.9 1501.62  4957.5 1492.98  4973.1 1491.50
  4991.4 1491.39  4991.9 1490.89  4996.9 1490.89  4997.4 1491.39  5010.0 1493.01
  5031.4 1494.57  5037.2 1494.22  5046.9 1500.69  5052.7 1497.62  5060.6 1502.46
  5068.3 1503.87  5074.1 1503.04  5083.9 1504.21  5111.1 1501.80  5118.9 1502.43
  5132.4 1512.41  5142.2 1517.69  5148.0 1518.09  5174.2 1523.78  5177.2 1523.78
#Mann=3,-1,0
  4885.6    0.05       0  4991.4    0.05       0  4997.4    0.05       0
Bank Sta=4991.4,4997.4
Exp/Cntr=0.3,0.1

Type RM Length L Ch R = 1,2404,467,467,467
BEGIN DESCRIPTION:
PYRAMID CREEK 5.0
END DESCRIPTION:
XS GIS Cut Line= 3
      2829555.66     10200703.12      2829672.50     10200640.00
      2829755.69     10200553.10
#Sta/Elev= 30
  4867.2 1508.70  4870.1 1508.70  4881.0 1507.32  4912.7 1500.45  4924.8 1496.17
  4935.3 1493.78  4941.0 1491.34  4946.8 1487.74  4957.2 1482.84  4962.9 1481.70
  4969.5 1479.27  4981.7 1478.54  4982.2 1478.04  4987.3 1478.04  4987.8 1478.54
  4992.3 1479.56  4999.0 1482.99  5007.2 1484.23  5014.1 1488.25  5021.4 1490.17
  5028.3 1492.98  5042.5 1496.58  5049.7 1498.06  5063.8 1500.13  5070.8 1501.85
  5078.0 1502.80  5099.1 1506.71  5113.2 1509.87  5116.8 1511.46  5120.3 1511.46
#Mann=3,-1,0
  4867.2    0.05       0  4981.7    0.05       0  4987.8    0.05       0
Bank Sta=4981.7,4987.8
Exp/Cntr=0.3,0.1

Type RM Length L Ch R = 1,1937,492,492,492
BEGIN DESCRIPTION:
PYRAMID CREEK 4.0
END DESCRIPTION:
XS GIS Cut Line= 3
      2829905.70     10201003.10      2830010.00     10200931.00
      2830405.67     10200703.12
#Sta/Elev= 30
  4873.2 1498.60  4901.6 1496.07  4931.3 1491.92  4937.4 1490.15  4946.1 1489.78
  4952.3 1486.55  4958.3 1482.20  5000.0 1480.67  5003.3 1479.32  5009.1 1479.91
  5018.1 1478.97  5037.5 1478.67  5038.0 1478.17  5043.7 1478.67  5083.8 1485.65
  5089.5 1487.42  5142.7 1495.64  5179.7 1502.60  5201.6 1508.05  5250.4 1516.13
  5287.8 1527.83  5295.1 1530.88  5309.4 1532.97  5352.8 1542.55  5384.0 1547.83
  5398.9 1551.21  5422.5 1558.63  5433.5 1562.88  5453.7 1567.75  5456.6 1567.75
#Mann=4,-1,0
  4873.2    0.05       0  5037.5    0.05       0  5043.7    0.05       0
  5422.5    0.12       0
Bank Sta=5037.5,5043.7
Exp/Cntr=0.3,0.1

Type RM Length L Ch R = 1,1445,449,449,449
BEGIN DESCRIPTION:
PYRAMID CREEK 3.0
END DESCRIPTION:
XS GIS Cut Line= 3
      2829855.65     10201253.09      2829982.75     10201332.00
      2830055.66     10201353.10
#Sta/Elev= 30
  4850.4 1496.00  4853.4 1496.00  4858.1 1495.43  4864.0 1494.48  4873.5 1493.56
  4879.4 1492.56  4885.7 1491.24  4894.7 1489.13  4900.6 1489.08  4909.3 1486.83
  4916.0 1482.52  4921.9 1482.22  4931.3 1479.86  4968.0 1479.38  4973.8 1479.21
  4989.2 1479.12  4995.1 1478.91  5013.5 1478.99  5017.2 1478.78  5017.7 1478.28
  5022.9 1478.28  5023.4 1478.78  5025.5 1478.82  5034.3 1480.24  5044.7 1482.73
  5053.9 1485.42  5059.1 1485.11  5065.5 1487.46  5073.3 1490.55  5075.9 1490.55
#Mann=3,-1,0
  4850.4    0.05       0  5017.2    0.05       0  5023.4    0.05       0
Bank Sta=5017.2,5023.4
Exp/Cntr=0.3,0.1

Type RM Length L Ch R = 1,996,189,189,189
BEGIN DESCRIPTION:
PYRAMID CREEK 2.0
END DESCRIPTION:
XS GIS Cut Line= 3
      2830005.70     10201703.11      2830183.50     10201625.00
      2830355.66     10201303.15
#Sta/Elev= 30
  4805.8 1491.86  4843.5 1488.57  4866.9 1487.84  4872.4 1485.92  4895.7 1483.85
  4913.6 1483.79  4925.9 1481.69  4936.9 1481.02  4942.4 1479.48  4965.8 1479.75
  5014.0 1478.92  5014.5 1478.42  5019.8 1478.42  5020.3 1478.92  5070.2 1478.98
  5092.9 1483.17  5099.3 1485.54  5126.9 1490.11  5203.3 1499.82  5217.6 1500.31
  5269.1 1505.06  5291.1 1505.63  5297.0 1507.27  5319.7 1509.47  5329.3 1509.80
  5335.0 1508.94  5342.4 1509.45  5356.9 1514.23  5362.2 1517.18  5365.0 1517.18
#Mann=3,-1,0
  4805.8    0.05       0  5014.0    0.05       0  5020.3    0.05       0
Bank Sta=5014,5020.3
Exp/Cntr=0.3,0.1

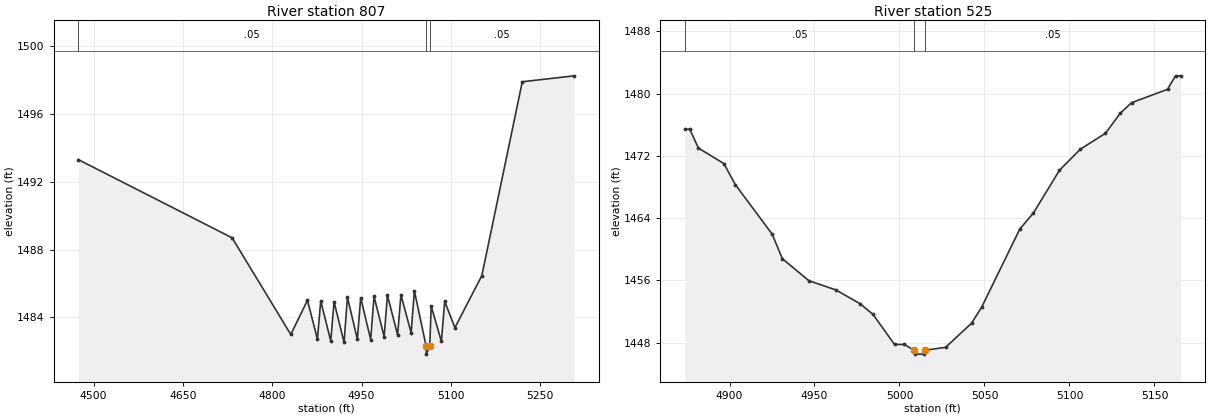
Type RM Length L Ch R = 1,807,282,282,282
BEGIN DESCRIPTION:
Mapping XS 96faf830
END DESCRIPTION:
XS GIS Cut Line= 4
      2830092.72     10202184.67      2830243.08     10201926.04
      2830333.29     10201745.62      2830476.88     10201446.48
#Sta/Elev= 30
  4474.4 1493.31  4732.7 1488.69  4831.2 1482.98  4859.2 1485.00  4875.9 1482.71
  4881.5 1484.96  4898.3 1482.60  4903.9 1484.91  4920.7 1482.51  4926.3 1485.18
  4943.0 1482.70  4948.6 1485.15  4965.4 1482.68  4971.0 1485.23  4988.0 1482.85
  4993.5 1485.30  5010.6 1482.95  5016.2 1485.32  5033.3 1483.08  5038.8 1485.56
  5058.3 1482.32  5058.8 1481.82  5064.6 1482.32  5067.0 1484.66  5084.1 1482.57
  5089.7 1484.94  5106.8 1483.38  5152.1 1486.46  5220.0 1497.91  5307.1 1498.26
#Mann=3,-1,0
  4474.4    0.05       0  5058.3    0.05       0  5064.6    0.05       0
Bank Sta=5058.3,5064.6
Exp/Cntr=0.3,0.1

Type RM Length L Ch R = 1,525,0,0,0
BEGIN DESCRIPTION:
PYRAMID CREEK 1.0
END DESCRIPTION:
XS GIS Cut Line= 3
      2830505.67     10202003.13      2830567.50     10201893.00
      2830655.70     10201753.08
#Sta/Elev= 30
  4873.7 1475.44  4876.6 1475.44  4881.7 1473.01  4896.7 1471.02  4903.4 1468.32
  4925.1 1461.95  4931.1 1458.80  4946.7 1455.97  4962.7 1454.78  4976.9 1453.00
  4984.4 1451.65  4997.1 1447.78  5002.9 1447.78  5008.6 1447.04  5009.1 1446.54
  5014.4 1446.54  5014.9 1447.04  5027.1 1447.41  5042.4 1450.51  5048.3 1452.55
  5070.8 1462.61  5078.8 1464.67  5094.1 1470.15  5106.3 1472.85  5121.2 1474.91
  5129.9 1477.49  5136.5 1478.83  5157.7 1480.56  5162.4 1482.29  5165.4 1482.29
#Mann=3,-1,0
  4873.7    0.05       0  5008.6    0.03       0  5014.9    0.05       0
Bank Sta=5008.6,5014.9
Exp/Cntr=0.3,0.1

Chan Stop Cuts=-1