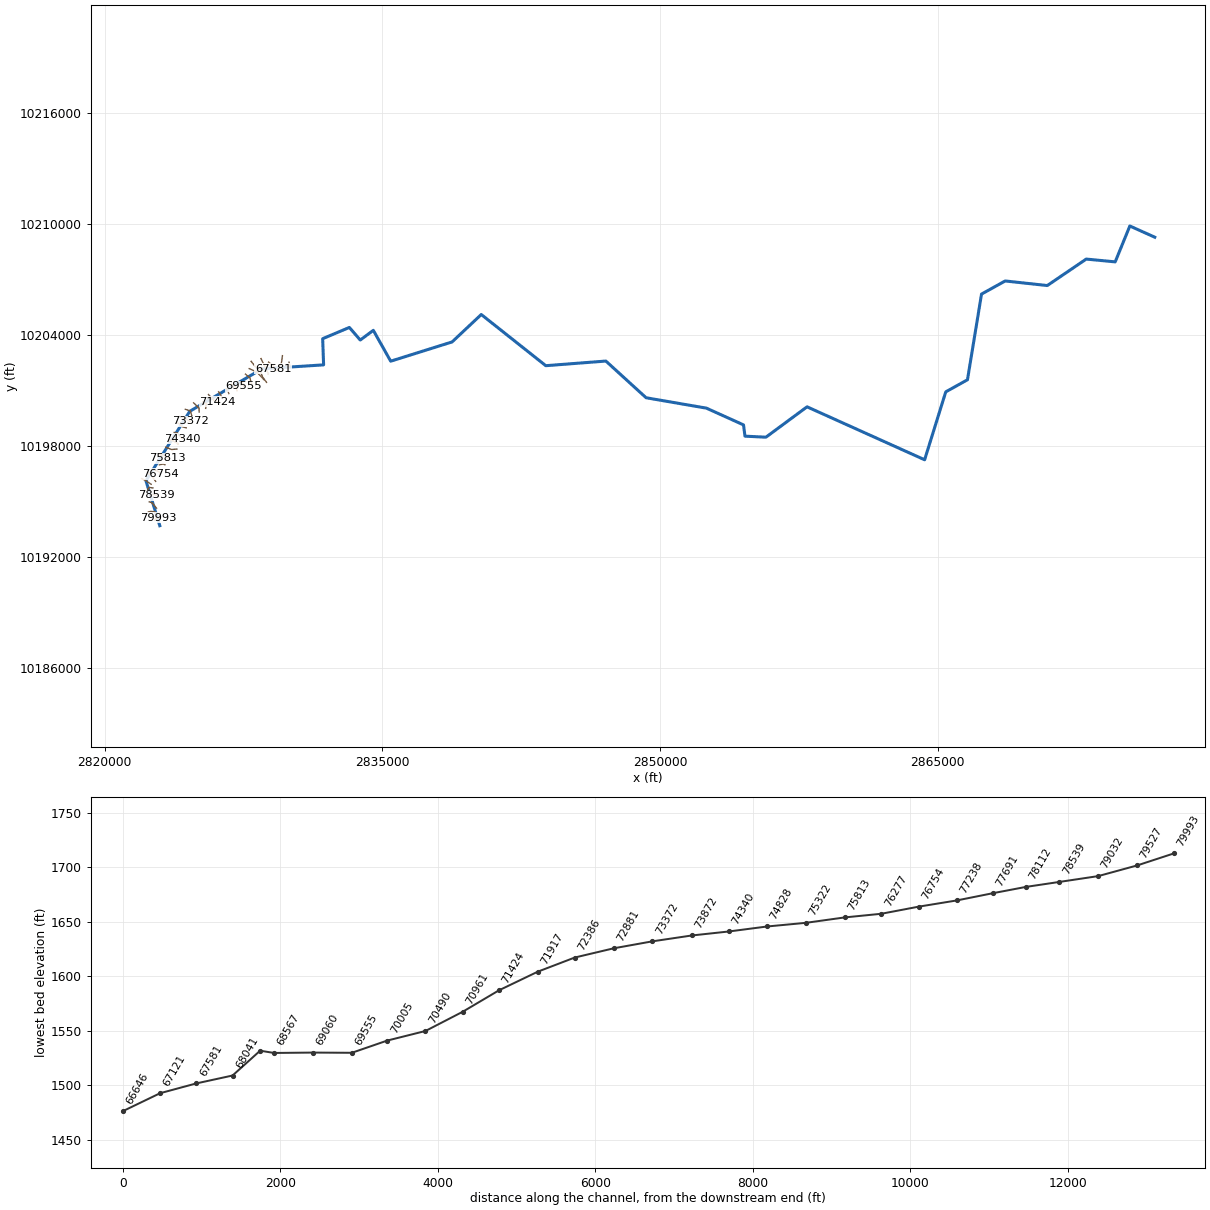
--- HONEY CREEK.prj (project) ---

Proj Title=HONEY CREEK Base Level Engineering
Current Plan=p01
Default Exp/Contr=0.3,0.1
English Units
Geom File=g01
Flow File=f01
Plan File=p01
Y Axis Title=Elevation
X Axis Title(PF)=Main Channel Distance
X Axis Title(XS)=Station
BEGIN DESCRIPTION:
HONEY CREEK
END DESCRIPTION:
DSS Export Rating Curves= 0
DSS Export Rating Curve Sorted= 0
DSS Export Volume Flow Curves= 0
DXF OffsetX= 0
DXF OffsetY= 0
DXF ScaleX= 1
DXF ScaleY= 10

--- HONEY CREEK.p01 (plan) ---

Plan Title=Multiple Run
Short Identifier=Multiple
Geom File=g01
Flow File=f01
Subcritical Flow
K Sum by GR= 0
Std Step Tol= 0.01
Critical Tol= 0.01
Num of Std Step Trials= 20
Max Error Tol= 0.3
Flow Tol Ratio= 0.001
Split Flow NTrial= 30
Split Flow Tol= 0.02
Split Flow Ratio= 0.02
Log Output Level= 0
Friction Slope Method= 1
Unsteady Friction Slope Method= 2
Unsteady Bridges Friction Slope Method= 1
Parabolic Critical Depth
Global Vel Dist=  1 , 1 , 1
Global Log Level= 0
CheckData=True
Encroach Param= -1, 0, 0, 0
BEGIN DESCRIPTION:
Multiple Run
END DESCRIPTION:

--- HONEY CREEK.f01 (steady flow) ---

Flow Title=Multiple
Program Version=4.10
Number of Profiles= 7
Profile Names=10-year,25-year,50-year,1pct_min,100-year,1pct_plu,500-year
River Rch & RM=HONEY CREEK,Reach-1         ,79993
      68     128     199     103     311     939     816
River Rch & RM=HONEY CREEK,Reach-1         ,69060
      82     159     250     131     395    1192    1055
River Rch & RM=HONEY CREEK,Reach-1         ,65684
     161     343     562     303     916    2766    2593
River Rch & RM=HONEY CREEK,Reach-1         ,64687
     225     493     821     449    1355    4092    3924
River Rch & RM=HONEY CREEK,Reach-1         ,56459
     247     544     910     499    1506    4549    4387
River Rch & RM=HONEY CREEK,Reach-1         ,53057
     265     589     988     543    1639    4949    4794
River Rch & RM=HONEY CREEK,Reach-1         ,51182
     275     613    1030     566    1710    5165    5015
River Rch & RM=HONEY CREEK,Reach-1         ,50610
     301     676    1138     628    1895    5724    5586
River Rch & RM=HONEY CREEK,Reach-1         ,48815
     353     800    1355     751    2269    6852    6747
River Rch & RM=HONEY CREEK,Reach-1         ,41655
     374     852    1446     803    2424    7320    7230
River Rch & RM=HONEY CREEK,Reach-1         ,36743
     395     900    1530     851    2569    7759    7685
River Rch & RM=HONEY CREEK,Reach-1         ,33302
     613    1432    2465    1386    4185   12640   12786
River Rch & RM=HONEY CREEK,Reach-1         ,26244
     618    1443    2486    1398    4221   12747   12899
River Rch & RM=HONEY CREEK,Reach-1         ,22450
     683    1601    2764    1558    4704   14207   14438
River Rch & RM=HONEY CREEK,Reach-1         ,22013
     745    1754    3036    1714    5177   15635   15948
River Rch & RM=HONEY CREEK,Reach-1         ,17183
     762    1796    3109    1757    5305   16021   16357
River Rch & RM=HONEY CREEK,Reach-1         ,11993
     917    2179    3790    2150    6492   19605   20163
River Rch & RM=HONEY CREEK,Reach-1         ,4127
     927    2202    3831    2173    6563   19819   20390
Boundary for River Rch & Prof#=HONEY CREEK,Reach-1         , 1
Up Type= 0
Dn Type= 3
Dn Slope=0.0005
Boundary for River Rch & Prof#=HONEY CREEK,Reach-1         , 2
Up Type= 0
Dn Type= 3
Dn Slope=0.0005
Boundary for River Rch & Prof#=HONEY CREEK,Reach-1         , 3
Up Type= 0
Dn Type= 3
Dn Slope=0.0005
Boundary for River Rch & Prof#=HONEY CREEK,Reach-1         , 4
Up Type= 0
Dn Type= 3
Dn Slope=0.0005
Boundary for River Rch & Prof#=HONEY CREEK,Reach-1         , 5
Up Type= 0
Dn Type= 3
Dn Slope=0.0005
Boundary for River Rch & Prof#=HONEY CREEK,Reach-1         , 6
Up Type= 0
Dn Type= 3
Dn Slope=0.0005
Boundary for River Rch & Prof#=HONEY CREEK,Reach-1         , 7
Up Type= 0
Dn Type= 3
Dn Slope=0.0005
DSS Import GetInterval= 0
DSS Import GetPeak= 0
DSS Import FillOption= 0

--- HONEY CREEK.g01 (geometry) ---

Geom Title=Existing Conditions

River Reach=HONEY CREEK,Reach-1
Reach XY= 30
      2822976.75     10193710.00      2822228.50     10196142.00
      2824596.50     10199895.00      2828498.50     10202190.00
      2831827.25     10202405.00      2831776.50     10203820.00
      2833220.25     10204428.00      2833806.75     10203747.00
      2834513.00     10204272.00      2835452.25     10202604.00
      2838768.25     10203644.00      2840345.50     10205127.00
      2843832.00     10202360.00      2847076.75     10202611.00
      2849251.75     10200627.00      2852511.00     10200065.00
      2854514.25     10199160.00      2854592.00     10198551.00
      2855725.00     10198495.00      2857946.25     10200137.00
      2864298.50     10197275.00      2865440.50     10200945.00
      2866613.50     10201600.00      2867373.25     10206232.00
      2868652.50     10206941.00      2870925.75     10206693.00
      2873030.50     10208124.00      2874595.25     10207973.00
      2875386.25     10209912.00      2876733.00     10209306.00

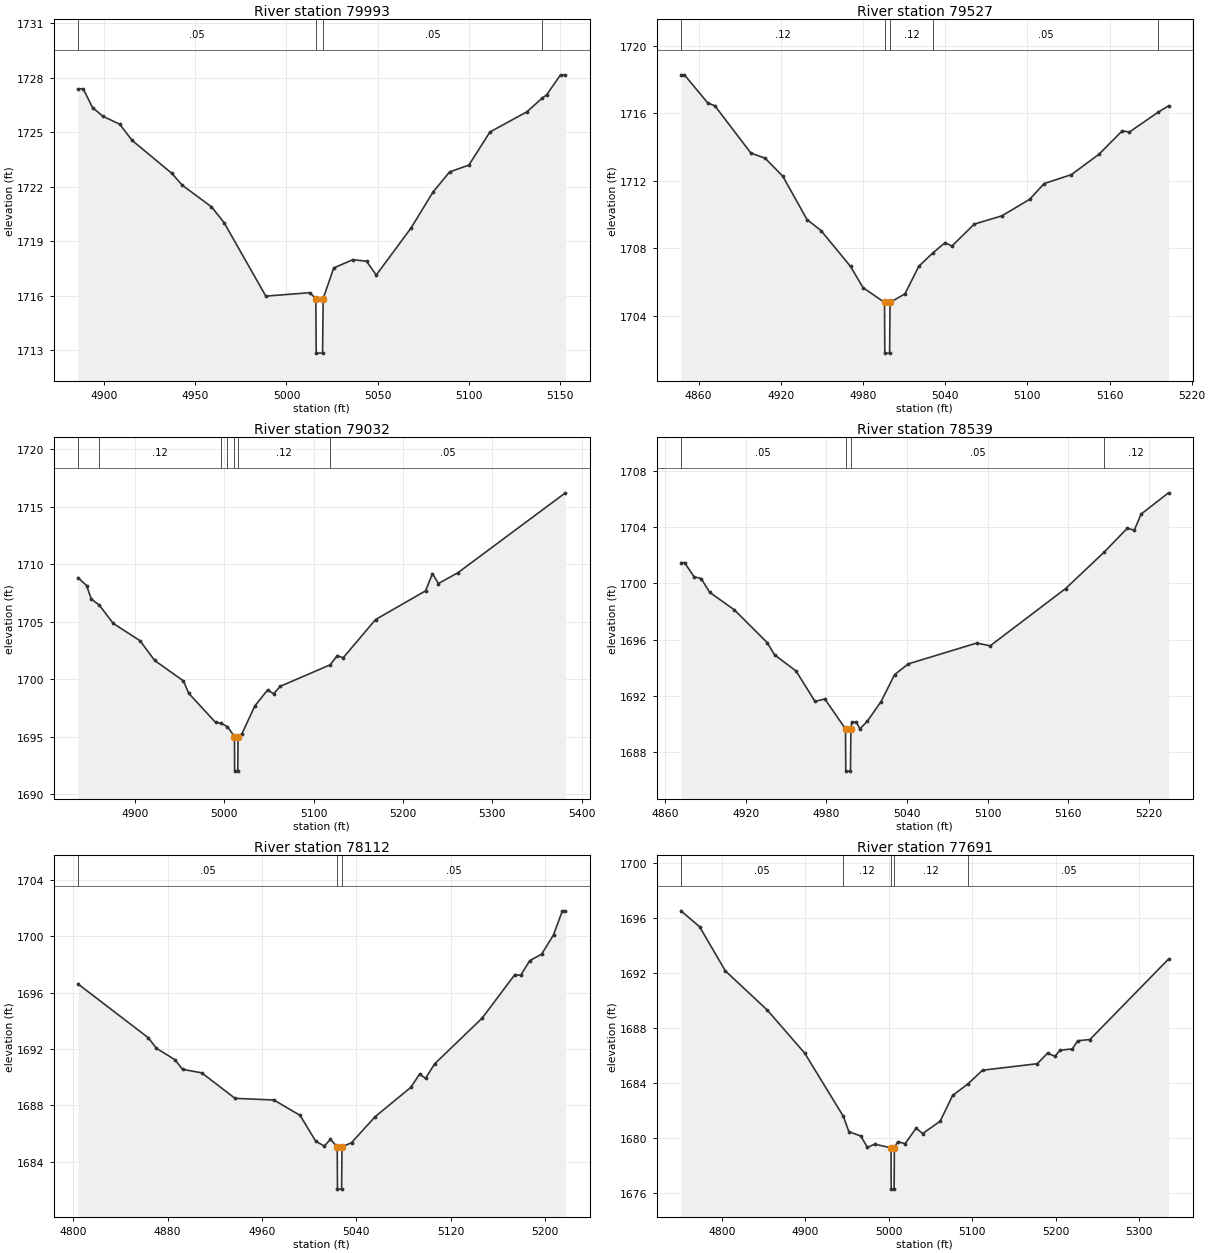
Type RM Length L Ch R = 1,79993,466,466,466
BEGIN DESCRIPTION:
HONEY CREEK 153.0
END DESCRIPTION:
XS GIS Cut Line= 3
      2822705.69     10194003.11      2822761.25     10194103.00
      2822905.70     10194153.12
#Sta/Elev= 30
  4885.7 1727.39  4888.6 1727.39  4893.7 1726.36  4899.4 1725.88  4908.6 1725.44
  4915.4 1724.55  4937.2 1722.73  4942.9 1722.08  4958.9 1720.89  4965.8 1720.02
  4988.7 1715.97  5012.8 1716.16  5016.1 1715.83  5016.3 1712.83  5019.8 1712.83
  5020.1 1715.83  5025.9 1717.52  5036.4 1717.98  5043.9 1717.89  5049.2 1717.13
  5068.2 1719.71  5080.3 1721.70  5089.4 1722.81  5100.0 1723.19  5111.5 1725.01
  5131.7 1726.12  5140.1 1726.87  5142.6 1727.06  5150.2 1728.16  5152.9 1728.16
#Mann=4,-1,0
  4885.7    0.05       0  5016.1    0.05       0  5020.1    0.05       0
  5140.1    0.12       0
Bank Sta=5016.1,5020.1
Exp/Cntr=0.3,0.1

Type RM Length L Ch R = 1,79527,495,495,495
BEGIN DESCRIPTION:
HONEY CREEK 152.0
END DESCRIPTION:
XS GIS Cut Line= 3
      2822355.71     10194453.12      2822505.25     10194485.00
      2822705.73     10194453.10
#Sta/Elev= 30
  4847.1 1718.28  4849.6 1718.28  4866.7 1716.61  4871.8 1716.45  4898.2 1713.64
  4908.4 1713.35  4921.4 1712.28  4939.1 1709.71  4949.3 1709.06  4970.9 1706.93
  4980.0 1705.68  4995.7 1704.80  4995.9 1701.80  4999.4 1701.80  4999.7 1704.80
  5010.6 1705.31  5020.7 1706.94  5030.9 1707.73  5039.9 1708.34  5044.9 1708.14
  5061.2 1709.44  5081.4 1709.93  5101.7 1710.91  5112.2 1711.84  5132.1 1712.37
  5152.3 1713.58  5169.3 1714.97  5174.4 1714.89  5195.3 1716.06  5203.0 1716.44
#Mann=5,-1,0
  4847.1    0.12       0  4995.7    0.07       0  4999.7    0.12       0
  5030.9    0.05       0  5195.3    0.12       0
Bank Sta=4995.7,4999.7
Exp/Cntr=0.3,0.1

Type RM Length L Ch R = 1,79032,493,493,493
BEGIN DESCRIPTION:
HONEY CREEK 151.0
END DESCRIPTION:
XS GIS Cut Line= 3
      2822405.64     10195003.13      2822558.50     10194944.00
      2822805.67     10194653.13
#Sta/Elev= 30
  4836.1 1708.82  4845.8 1708.14  4851.1 1706.96  4860.1 1706.43  4875.7 1704.84
  4905.6 1703.34  4921.9 1701.63  4954.1 1699.85  4960.2 1698.76  4990.1 1696.24
  4995.8 1696.18  5003.5 1695.86  5011.3 1695.00  5011.5 1692.00  5015.0 1692.00
  5015.3 1695.00  5019.8 1695.27  5034.1 1697.67  5048.4 1699.06  5055.0 1698.73
  5062.7 1699.38  5118.3 1701.24  5126.4 1702.05  5132.9 1701.85  5169.2 1705.18
  5225.2 1707.68  5232.9 1709.17  5239.5 1708.31  5261.5 1709.26  5381.7 1716.20
#Mann=7,-1,0
  4836.1    0.05       0  4860.1    0.12       0  4995.8    0.05       0
  5003.5    0.12       0  5011.3    0.05       0  5015.3    0.12       0
  5118.3    0.05       0
Bank Sta=5011.3,5015.3
Exp/Cntr=0.3,0.1

Type RM Length L Ch R = 1,78539,427,427,427
BEGIN DESCRIPTION:
HONEY CREEK 150.0
END DESCRIPTION:
XS GIS Cut Line= 3
      2822455.69     10195353.11      2822575.50     10195399.00
      2822805.67     10195353.11
#Sta/Elev= 30
  4871.7 1701.46  4874.4 1701.46  4881.4 1700.46  4886.7 1700.33  4893.1 1699.35
  4911.4 1698.11  4935.9 1695.78  4941.4 1694.91  4957.4 1693.76  4971.5 1691.60
  4978.8 1691.78  4994.2 1689.65  4994.4 1686.65  4997.9 1686.65  4998.2 1689.65
  4998.8 1690.13  5002.3 1690.13  5004.9 1689.65  5010.4 1690.19  5020.6 1691.58
  5030.8 1693.51  5041.0 1694.27  5092.0 1695.75  5101.9 1695.55  5158.1 1699.62
  5186.7 1702.20  5204.1 1703.91  5209.2 1703.76  5214.3 1704.91  5234.7 1706.42
#Mann=4,-1,0
  4871.7    0.05       0  4994.2    0.05       0  4998.2    0.05       0
  5186.7    0.12       0
Bank Sta=4994.2,4998.2
Exp/Cntr=0.3,0.1

Type RM Length L Ch R = 1,78112,421,421,421
BEGIN DESCRIPTION:
HONEY CREEK 149.0
END DESCRIPTION:
XS GIS Cut Line= 3
      2822305.67     10195603.07      2822390.00     10195780.00
      2822605.73     10195753.11
#Sta/Elev= 30
  4804.0 1696.63  4863.6 1692.81  4870.5 1692.06  4886.3 1691.24  4892.7 1690.56
  4909.0 1690.31  4937.2 1688.50  4970.2 1688.38  4992.4 1687.29  5005.7 1685.45
  5013.0 1685.11  5018.1 1685.59  5023.9 1685.05  5024.1 1682.05  5027.6 1682.05
  5027.9 1685.05  5036.0 1685.35  5056.1 1687.20  5086.3 1689.28  5093.7 1690.22
  5098.8 1689.92  5106.5 1690.95  5146.8 1694.20  5174.5 1697.29  5179.5 1697.24
  5187.1 1698.28  5197.2 1698.74  5207.3 1700.11  5214.8 1701.82  5217.4 1701.82
#Mann=3,-1,0
  4804.0    0.05       0  5023.9    0.05       0  5027.9    0.05       0
Bank Sta=5023.9,5027.9
Exp/Cntr=0.3,0.1

Type RM Length L Ch R = 1,77691,453,453,453
BEGIN DESCRIPTION:
HONEY CREEK 148.0
END DESCRIPTION:
XS GIS Cut Line= 3
      2822005.67     10196253.12      2822228.50     10196142.00
      2822505.66     10195953.13
#Sta/Elev= 30
  4751.0 1696.49  4773.4 1695.33  4804.2 1692.12  4854.5 1689.27  4899.3 1686.14
  4945.7 1681.54  4952.2 1680.43  4966.4 1680.12  4974.5 1679.29  4983.2 1679.52
  5002.8 1679.25  5003.0 1676.25  5006.5 1676.25  5006.8 1679.25  5010.8 1679.70
  5019.7 1679.56  5032.9 1680.69  5040.7 1680.29  5061.7 1681.19  5076.6 1683.06
  5095.3 1683.92  5112.5 1684.90  5178.1 1685.37  5190.4 1686.14  5199.3 1685.91
  5205.3 1686.35  5220.2 1686.45  5226.5 1687.04  5241.2 1687.13  5335.4 1692.98
#Mann=5,-1,0
  4751.0    0.05       0  4945.7    0.12       0  5002.8    0.07       0
  5006.8    0.12       0  5095.3    0.05       0
Bank Sta=5002.8,5006.8
Exp/Cntr=0.3,0.1

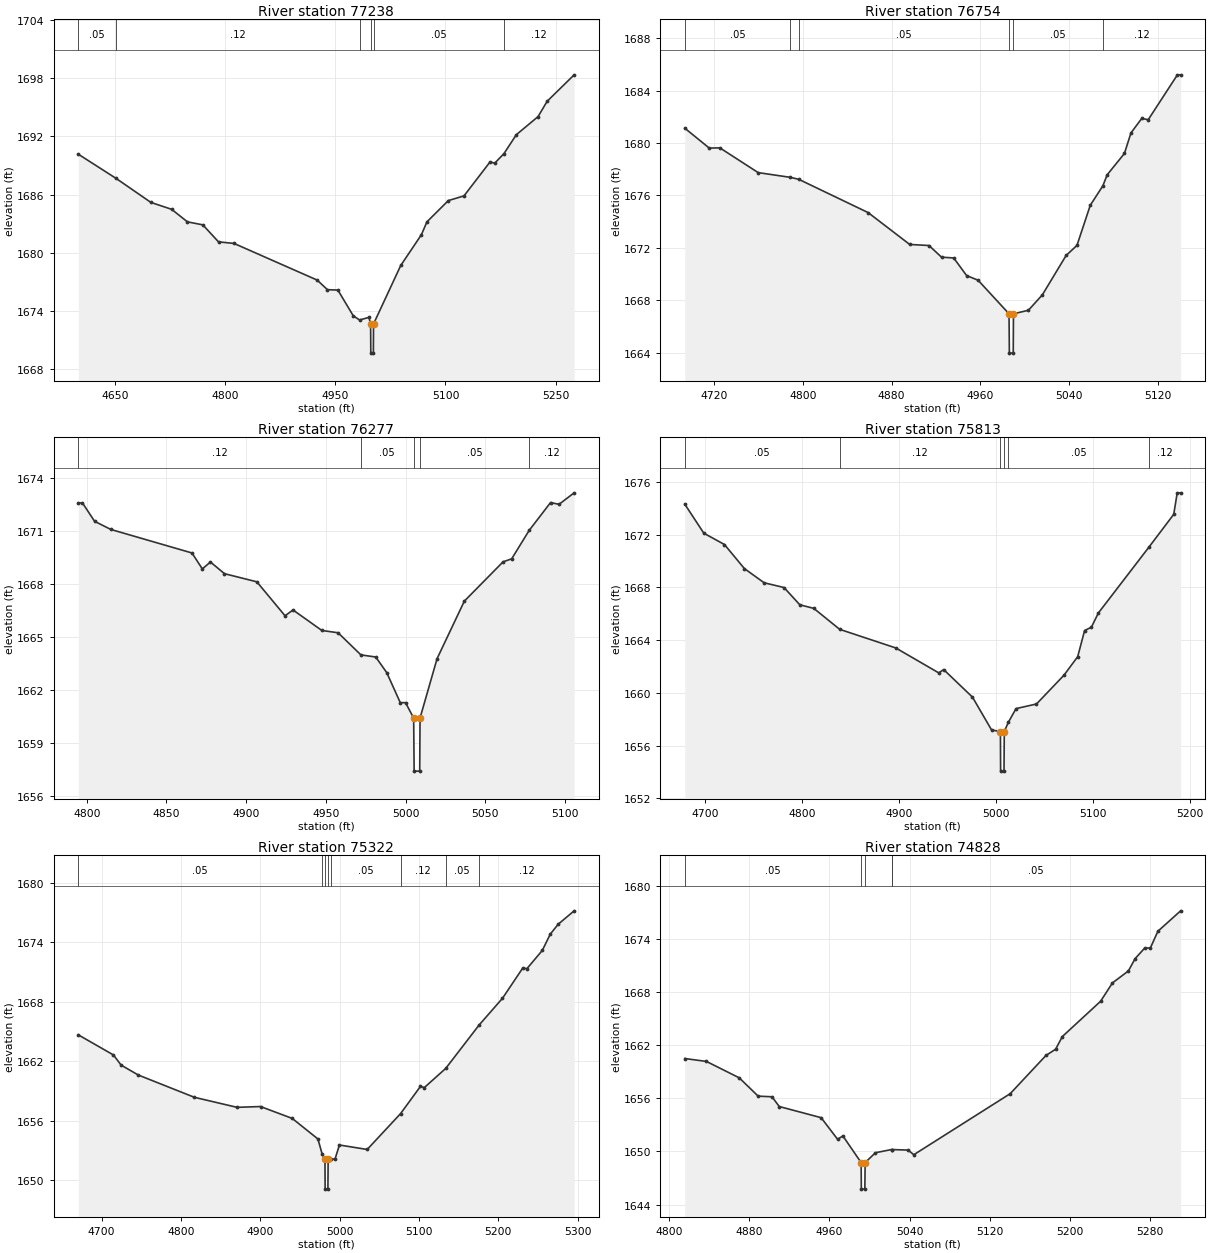
Type RM Length L Ch R = 1,77238,484,484,484
BEGIN DESCRIPTION:
HONEY CREEK 147.0
END DESCRIPTION:
XS GIS Cut Line= 3
      2822305.69     10196603.11      2822596.75     10196328.00
      2822755.69     10196103.10
#Sta/Elev= 30
  4599.5 1690.15  4651.0 1687.66  4698.4 1685.19  4726.7 1684.48  4748.2 1683.19
  4769.2 1682.88  4790.6 1681.13  4811.7 1680.97  4925.0 1677.20  4939.1 1676.21
  4953.3 1676.17  4974.3 1673.52  4982.9 1673.09  4995.7 1673.36  4997.9 1672.68
  4998.2 1669.68  5001.7 1669.68  5001.9 1672.68  5039.0 1678.70  5067.2 1681.87
  5074.7 1683.19  5103.9 1685.38  5125.2 1685.86  5160.9 1689.37  5167.0 1689.22
  5179.7 1690.21  5196.6 1692.16  5226.2 1694.02  5238.6 1695.60  5275.4 1698.32
#Mann=6,-1,0
  4599.5    0.05       0  4651.0    0.12       0  4982.9    0.05       0
  4997.9    0.05       0  5001.9    0.05       0  5179.7    0.12       0
Bank Sta=4997.9,5001.9
Exp/Cntr=0.3,0.1

Type RM Length L Ch R = 1,76754,477,477,477
BEGIN DESCRIPTION:
HONEY CREEK 146.0
END DESCRIPTION:
XS GIS Cut Line= 3
      2822655.66     10196753.12      2822933.75     10196624.00
      2823005.70     10196503.09
#Sta/Elev= 30
  4693.4 1681.13  4715.5 1679.61  4725.0 1679.63  4759.6 1677.74  4788.6 1677.38
  4796.2 1677.23  4858.8 1674.69  4896.3 1672.26  4913.7 1672.18  4925.0 1671.29
  4936.0 1671.23  4947.6 1669.89  4958.0 1669.53  4985.9 1666.97  4986.2 1663.97
  4989.7 1663.97  4989.9 1666.97  5003.4 1667.24  5016.0 1668.42  5037.4 1671.42
  5047.2 1672.19  5059.2 1675.25  5070.6 1676.74  5074.4 1677.57  5090.0 1679.20
  5095.9 1680.77  5105.6 1681.87  5111.5 1681.78  5137.8 1685.20  5140.7 1685.20
#Mann=6,-1,0
  4693.4    0.05       0  4788.6    0.12       0  4796.2    0.05       0
  4985.9    0.05       0  4989.9    0.05       0  5070.6    0.12       0
Bank Sta=4985.9,4989.9
Exp/Cntr=0.3,0.1

Type RM Length L Ch R = 1,76277,464,464,464
BEGIN DESCRIPTION:
HONEY CREEK 145.0
END DESCRIPTION:
XS GIS Cut Line= 3
      2822955.67     10197003.11      2823157.25     10197042.00
      2823255.65     10197003.13
#Sta/Elev= 30
  4794.7 1672.57  4797.3 1672.57  4804.9 1671.53  4815.1 1671.07  4866.0 1669.74
  4872.5 1668.84  4877.6 1669.23  4886.4 1668.57  4906.7 1668.11  4924.4 1666.19
  4929.4 1666.52  4947.5 1665.36  4957.7 1665.23  4972.0 1663.98  4981.3 1663.86
  4988.2 1662.98  4996.7 1661.28  5000.0 1661.28  5005.1 1660.41  5005.4 1657.41
  5008.9 1657.41  5009.1 1660.41  5019.8 1663.77  5036.9 1667.02  5061.2 1669.24
  5066.6 1669.41  5077.6 1671.02  5091.0 1672.59  5096.3 1672.49  5105.8 1673.14
#Mann=5,-1,0
  4794.7    0.12       0  4972.0    0.05       0  5005.1    0.05       0
  5009.1    0.05       0  5077.6    0.12       0
Bank Sta=5005.1,5009.1
Exp/Cntr=0.3,0.1

Type RM Length L Ch R = 1,75813,491,491,491
BEGIN DESCRIPTION:
HONEY CREEK 144.0
END DESCRIPTION:
XS GIS Cut Line= 3
      2822955.65     10197553.12      2823269.25     10197486.00
      2823405.72     10197353.08
#Sta/Elev= 30
  4679.3 1674.31  4698.9 1672.11  4720.2 1671.25  4740.7 1669.43  4761.1 1668.35
  4781.6 1667.99  4797.9 1666.68  4812.3 1666.41  4839.0 1664.82  4896.8 1663.41
  4941.1 1661.52  4946.2 1661.77  4975.9 1659.68  4995.6 1657.19  5004.7 1657.07
  5004.9 1654.07  5008.4 1654.07  5008.7 1657.07  5012.8 1657.76  5020.8 1658.81
  5041.9 1659.16  5070.2 1661.34  5084.4 1662.75  5091.5 1664.73  5098.5 1664.98
  5105.7 1666.06  5157.9 1671.06  5183.4 1673.54  5187.0 1675.17  5190.5 1675.17
#Mann=6,-1,0
  4679.3    0.05       0  4839.0    0.12       0  5004.7    0.07       0
  5008.7    0.12       0  5012.8    0.05       0  5157.9    0.12       0
Bank Sta=5004.7,5008.7
Exp/Cntr=0.3,0.1

Type RM Length L Ch R = 1,75322,494,494,494
BEGIN DESCRIPTION:
HONEY CREEK 143.0
END DESCRIPTION:
XS GIS Cut Line= 3
      2823305.69     10197953.11      2823611.00     10197830.00
      2823905.70     10197853.11
#Sta/Elev= 30
  4670.8 1664.68  4715.1 1662.65  4724.7 1661.63  4746.3 1660.63  4817.1 1658.38
  4870.8 1657.37  4900.4 1657.45  4940.4 1656.25  4972.7 1654.18  4977.9 1652.70
  4981.6 1652.12  4981.8 1649.12  4985.3 1649.12  4985.6 1652.12  4988.6 1652.13
  4994.3 1652.16  4999.8 1653.57  5034.8 1653.12  5076.9 1656.74  5101.9 1659.48
  5106.9 1659.37  5133.7 1661.29  5175.6 1665.65  5205.3 1668.37  5231.0 1671.44
  5236.0 1671.35  5255.5 1673.20  5265.5 1674.84  5275.5 1675.84  5295.6 1677.19
#Mann=8,-1,0
  4670.8    0.05       0  4977.9    0.12       0  4981.6    0.05       0
  4985.6    0.12       0  4988.6    0.05       0  5076.9    0.12       0
  5133.7    0.05       0  5175.6    0.12       0
Bank Sta=4981.6,4985.6
Exp/Cntr=0.3,0.1

Type RM Length L Ch R = 1,74828,488,488,488
BEGIN DESCRIPTION:
HONEY CREEK 142.0
END DESCRIPTION:
XS GIS Cut Line= 3
      2823505.68     10198353.11      2823681.75     10198299.00
      2823955.72     10198153.09
#Sta/Elev= 30
  4815.8 1660.50  4837.4 1660.17  4870.1 1658.32  4889.0 1656.25  4902.8 1656.18
  4910.0 1655.08  4951.8 1653.82  4968.2 1651.38  4973.5 1651.76  4991.7 1648.75
  4991.9 1645.75  4995.4 1645.75  4995.7 1648.75  5006.0 1649.86  5022.0 1650.22
  5022.1 1650.22  5038.4 1650.16  5044.3 1649.64  5140.4 1656.53  5176.1 1660.85
  5185.7 1661.55  5192.4 1662.98  5230.6 1666.97  5242.4 1669.04  5258.3 1670.39
  5265.0 1671.78  5274.6 1672.98  5280.2 1672.98  5287.7 1674.87  5310.4 1677.18
#Mann=5,-1,0
  4815.8    0.05       0  4991.7    0.05       0  4995.7    0.05       0
  5022.0    0.12       0  5022.1    0.05       0
Bank Sta=4991.7,4995.7
Exp/Cntr=0.3,0.1

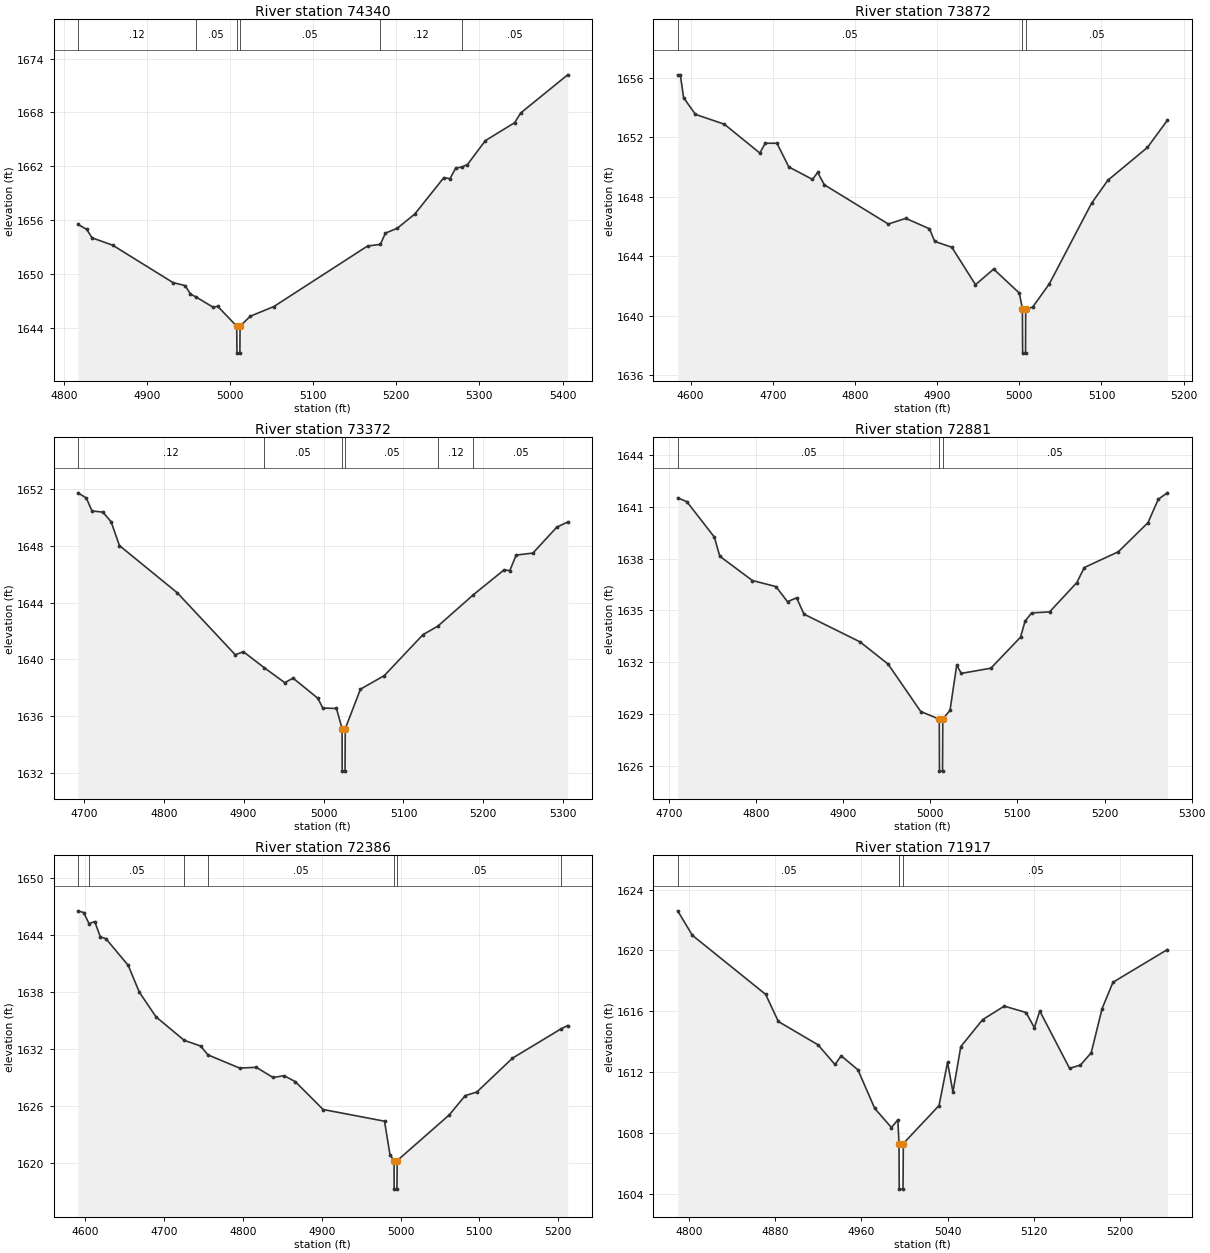
Type RM Length L Ch R = 1,74340,468,468,468
BEGIN DESCRIPTION:
HONEY CREEK 141.0
END DESCRIPTION:
XS GIS Cut Line= 3
      2823755.64     10198753.12      2823931.75     10198703.00
      2824205.71     10198403.09
#Sta/Elev= 30
  4816.9 1655.50  4827.3 1654.95  4833.9 1654.00  4858.5 1653.19  4931.3 1649.01
  4945.9 1648.68  4952.1 1647.75  4958.5 1647.43  4979.7 1646.26  4984.9 1646.38
  5007.9 1644.15  5008.2 1641.15  5011.7 1641.15  5011.9 1644.15  5024.1 1645.26
  5052.5 1646.34  5165.3 1653.09  5180.7 1653.28  5186.9 1654.53  5201.1 1655.07
  5222.1 1656.65  5257.2 1660.72  5264.6 1660.60  5271.4 1661.78  5278.9 1661.90
  5285.6 1662.18  5307.2 1664.85  5342.3 1666.84  5349.7 1667.93  5406.2 1672.18
#Mann=6,-1,0
  4816.9    0.12       0  4958.5    0.05       0  5007.9    0.05       0
  5011.9    0.05       0  5180.7    0.12       0  5278.9    0.05       0
Bank Sta=5007.9,5011.9
Exp/Cntr=0.3,0.1

Type RM Length L Ch R = 1,73872,500,500,500
BEGIN DESCRIPTION:
HONEY CREEK 140.0
END DESCRIPTION:
XS GIS Cut Line= 3
      2823905.71     10199303.09      2824230.00     10199043.00
      2824405.73     10199003.10
#Sta/Elev= 30
  4584.3 1656.21  4587.5 1656.21  4591.5 1654.67  4605.9 1653.55  4641.1 1652.89
  4684.3 1650.95  4690.7 1651.61  4705.1 1651.61  4719.5 1650.02  4748.3 1649.18
  4754.7 1649.65  4762.7 1648.82  4840.6 1646.18  4861.9 1646.56  4890.7 1645.86
  4897.1 1645.01  4917.9 1644.62  4946.7 1642.10  4968.8 1643.15  5000.0 1641.54
  5003.8 1640.50  5004.1 1637.50  5007.6 1637.50  5007.8 1640.50  5016.1 1640.58
  5036.6 1642.16  5087.9 1647.57  5107.8 1649.12  5156.0 1651.33  5180.2 1653.15
#Mann=3,-1,0
  4584.3    0.05       0  5003.8    0.05       0  5007.8    0.05       0
Bank Sta=5003.8,5007.8
Exp/Cntr=0.3,0.1

Type RM Length L Ch R = 1,73372,491,491,491
BEGIN DESCRIPTION:
HONEY CREEK 139.0
END DESCRIPTION:
XS GIS Cut Line= 3
      2824055.66     10199603.12      2824352.50     10199524.00
      2824605.72     10199353.09
#Sta/Elev= 30
  4692.8 1651.75  4703.2 1651.38  4710.3 1650.47  4723.9 1650.39  4734.2 1649.71
  4744.6 1648.03  4817.0 1644.70  4889.5 1640.33  4899.8 1640.54  4925.7 1639.42
  4951.5 1638.36  4961.9 1638.68  4992.9 1637.26  4999.1 1636.57  5016.2 1636.54
  5023.2 1635.12  5023.4 1632.12  5026.9 1632.12  5027.2 1635.12  5046.2 1637.90
  5076.1 1638.86  5124.5 1641.75  5142.9 1642.34  5187.5 1644.56  5226.0 1646.32
  5233.1 1646.26  5241.0 1647.36  5262.0 1647.50  5291.9 1649.33  5305.5 1649.69
#Mann=6,-1,0
  4692.8    0.12       0  4925.7    0.05       0  5023.2    0.05       0
  5027.2    0.05       0  5142.9    0.12       0  5187.5    0.05       0
Bank Sta=5023.2,5027.2
Exp/Cntr=0.3,0.1

Type RM Length L Ch R = 1,72881,495,495,495
BEGIN DESCRIPTION:
HONEY CREEK 138.0
END DESCRIPTION:
XS GIS Cut Line= 3
      2824355.67     10200003.12      2824631.75     10199915.00
      2824705.68     10199653.14
#Sta/Elev= 30
  4710.2 1641.50  4720.7 1641.28  4752.2 1639.24  4758.5 1638.13  4795.9 1636.73
  4822.9 1636.38  4836.2 1635.51  4846.7 1635.73  4855.1 1634.79  4919.4 1633.19
  4951.6 1631.91  4989.1 1629.17  5010.4 1628.73  5010.6 1625.73  5014.1 1625.73
  5014.4 1628.73  5022.7 1629.24  5030.4 1631.85  5035.6 1631.37  5069.6 1631.67
  5103.6 1633.46  5108.8 1634.38  5116.3 1634.86  5137.0 1634.92  5168.2 1636.61
  5176.8 1637.48  5215.9 1638.39  5249.9 1640.07  5261.7 1641.42  5272.1 1641.79
#Mann=3,-1,0
  4710.2    0.05       0  5010.4    0.05       0  5014.4    0.05       0
Bank Sta=5010.4,5014.4
Exp/Cntr=0.3,0.1

Type RM Length L Ch R = 1,72386,469,469,469
BEGIN DESCRIPTION:
HONEY CREEK 137.0
END DESCRIPTION:
XS GIS Cut Line= 3
      2824805.66     10200353.13      2825096.50     10200065.00
      2825105.68     10199853.10
#Sta/Elev= 30
  4590.6 1646.55  4597.7 1646.37  4604.6 1645.20  4611.8 1645.42  4618.9 1643.81
  4626.0 1643.62  4654.3 1640.81  4668.4 1637.99  4689.6 1635.39  4725.4 1632.92
  4746.2 1632.32  4755.5 1631.39  4795.7 1630.00  4816.9 1630.08  4838.1 1629.01
  4852.3 1629.20  4866.4 1628.57  4901.7 1625.64  4979.6 1624.41  4986.6 1620.87
  4991.7 1620.26  4991.9 1617.26  4995.4 1617.26  4995.7 1620.26  5061.9 1625.08
  5082.0 1627.10  5096.8 1627.48  5142.0 1631.04  5203.9 1634.14  5212.1 1634.48
#Mann=7,-1,0
  4590.6    0.12       0  4604.6    0.05       0  4725.4    0.12       0
  4755.5    0.05       0  4991.7    0.05       0  4995.7    0.05       0
  5203.9    0.12       0
Bank Sta=4991.7,4995.7
Exp/Cntr=0.3,0.1

Type RM Length L Ch R = 1,71917,493,493,493
BEGIN DESCRIPTION:
HONEY CREEK 136.0
END DESCRIPTION:
XS GIS Cut Line= 3
      2825305.72     10200403.09      2825486.00     10200295.00
      2825455.68     10200053.09
#Sta/Elev= 30
  4789.8 1622.60  4803.4 1620.99  4871.4 1617.10  4883.1 1615.32  4920.0 1613.78
  4935.6 1612.49  4941.4 1613.06  4956.9 1612.14  4972.5 1609.60  4988.0 1608.34
  4993.9 1608.85  4995.0 1607.29  4995.2 1604.29  4998.7 1604.29  4999.0 1607.29
  5032.1 1609.79  5040.0 1612.63  5045.0 1610.68  5052.3 1613.67  5072.5 1615.44
  5092.6 1616.33  5112.8 1615.91  5120.5 1614.91  5125.5 1616.01  5153.1 1612.24
  5163.2 1612.45  5173.2 1613.26  5183.3 1616.17  5193.4 1617.90  5243.8 1620.05
#Mann=3,-1,0
  4789.8    0.05       0  4995.0    0.05       0  4999.0    0.05       0
Bank Sta=4995,4999
Exp/Cntr=0.3,0.1

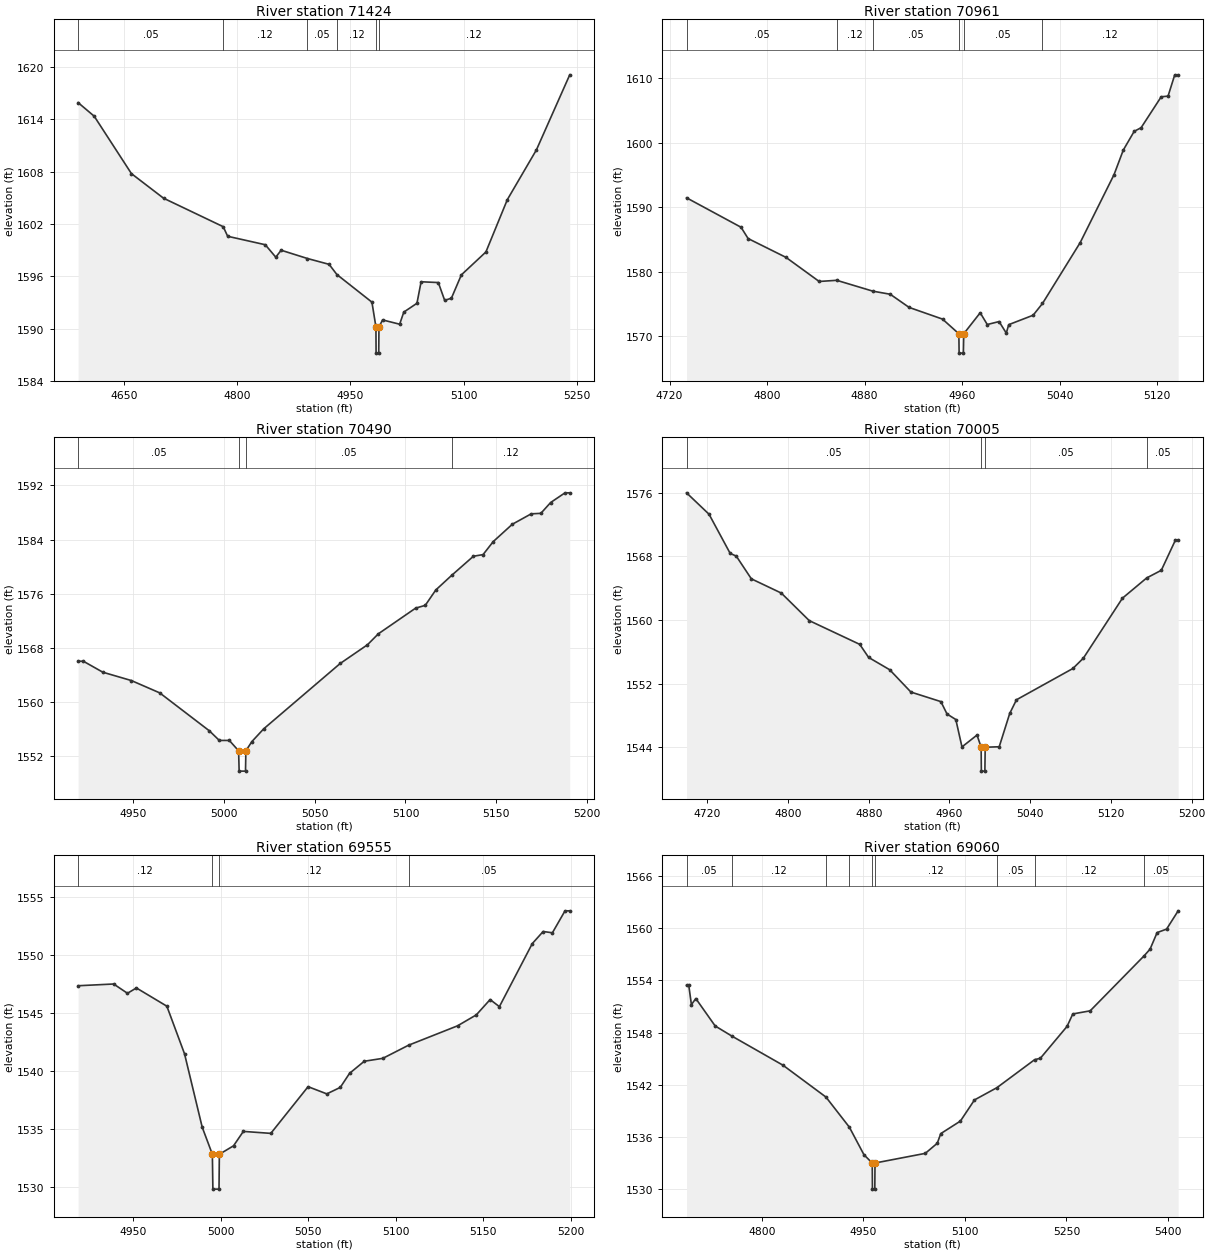
Type RM Length L Ch R = 1,71424,463,463,463
BEGIN DESCRIPTION:
HONEY CREEK 135.0
END DESCRIPTION:
XS GIS Cut Line= 3
      2825605.67     10200803.13      2825888.00     10200505.00
      2826105.64     10200403.13
#Sta/Elev= 30
  4589.4 1615.93  4610.7 1614.37  4660.0 1607.78  4702.5 1604.96  4781.5 1601.69
  4787.4 1600.59  4837.2 1599.62  4851.1 1598.19  4858.2 1598.99  4893.0 1598.04
  4921.7 1597.37  4932.0 1596.20  4978.4 1593.03  4983.7 1590.18  4983.9 1587.18
  4987.4 1587.18  4987.7 1590.18  4992.5 1590.99  5015.1 1590.50  5020.6 1591.89
  5038.0 1592.90  5043.5 1595.37  5066.3 1595.28  5074.7 1593.24  5083.6 1593.48
  5096.8 1596.16  5129.3 1598.79  5157.7 1604.80  5196.2 1610.51  5240.3 1619.12
#Mann=6,-1,0
  4589.4    0.05       0  4781.5    0.12       0  4893.0    0.05       0
  4932.0    0.12       0  4983.7    0.07       0  4987.7    0.12       0
Bank Sta=4983.7,4987.7
Exp/Cntr=0.3,0.1

Type RM Length L Ch R = 1,70961,471,471,471
BEGIN DESCRIPTION:
HONEY CREEK 134.0
END DESCRIPTION:
XS GIS Cut Line= 3
      2826155.70     10200953.09      2826292.75     10200725.00
      2826355.69     10200603.09
#Sta/Elev= 30
  4733.9 1591.46  4778.6 1586.90  4784.4 1585.15  4815.5 1582.23  4842.7 1578.50
  4857.1 1578.68  4886.7 1577.00  4901.0 1576.52  4916.5 1574.48  4943.9 1572.67
  4957.3 1570.40  4957.5 1567.40  4961.0 1567.40  4961.3 1570.40  4974.8 1573.65
  4980.6 1571.83  4990.3 1572.29  4996.2 1570.50  4998.2 1571.81  5018.2 1573.27
  5025.9 1575.09  5056.8 1584.51  5084.6 1595.05  5092.2 1598.86  5101.1 1601.75
  5106.8 1602.32  5123.3 1607.11  5128.9 1607.21  5134.4 1610.51  5137.2 1610.51
#Mann=6,-1,0
  4733.9    0.05       0  4857.1    0.12       0  4886.7    0.05       0
  4957.3    0.05       0  4961.3    0.05       0  5025.9    0.12       0
Bank Sta=4957.3,4961.3
Exp/Cntr=0.3,0.1

Type RM Length L Ch R = 1,70490,485,485,485
BEGIN DESCRIPTION:
HONEY CREEK 133.0
END DESCRIPTION:
XS GIS Cut Line= 3
      2826605.70     10201103.08      2826646.25     10201034.00
      2826705.68     10200853.11
#Sta/Elev= 30
  4919.9 1566.04  4922.8 1566.04  4933.5 1564.42  4949.2 1563.19  4964.8 1561.37
  4992.1 1555.77  4997.6 1554.35  5003.1 1554.35  5008.2 1552.82  5008.5 1549.82
  5012.0 1549.82  5012.2 1552.82  5015.5 1554.18  5022.0 1556.06  5064.1 1565.71
  5079.1 1568.47  5085.1 1570.09  5105.6 1573.88  5110.9 1574.29  5116.7 1576.56
  5125.4 1578.71  5137.4 1581.54  5142.7 1581.78  5148.3 1583.70  5158.8 1586.26
  5169.2 1587.80  5174.5 1587.87  5179.9 1589.47  5187.8 1590.90  5190.4 1590.90
#Mann=4,-1,0
  4919.9    0.05       0  5008.2    0.05       0  5012.2    0.05       0
  5125.4    0.12       0
Bank Sta=5008.2,5012.2
Exp/Cntr=0.3,0.1

Type RM Length L Ch R = 1,70005,450,450,450
BEGIN DESCRIPTION:
HONEY CREEK 132.0
END DESCRIPTION:
XS GIS Cut Line= 3
      2826855.71     10201353.09      2827102.75     10201182.00
      2827155.70     10201003.07
#Sta/Elev= 30
  4699.5 1575.98  4721.8 1573.29  4742.7 1568.38  4748.8 1568.03  4763.7 1565.18
  4793.4 1563.39  4821.1 1559.93  4871.1 1556.95  4879.9 1555.31  4900.8 1553.76
  4921.8 1550.96  4951.5 1549.76  4957.6 1548.20  4966.3 1547.51  4972.4 1544.07
  4987.3 1545.56  4991.4 1544.03  4991.6 1541.03  4995.1 1541.03  4995.4 1544.03
  5009.3 1544.09  5019.7 1548.27  5026.4 1549.99  5082.3 1553.92  5092.7 1555.22
  5131.4 1562.75  5155.4 1565.29  5169.9 1566.25  5183.9 1570.05  5186.6 1570.05
#Mann=4,-1,0
  4699.5    0.05       0  4991.4    0.07       0  4995.4    0.05       0
  5155.4    0.05       0
Bank Sta=4991.4,4995.4
Exp/Cntr=0.3,0.1

Type RM Length L Ch R = 1,69555,495,495,495
BEGIN DESCRIPTION:
HONEY CREEK 131.0
END DESCRIPTION:
XS GIS Cut Line= 3
      2827355.66     10201453.12      2827436.00     10201440.00
      2827505.70     10201253.07
#Sta/Elev= 30
  4918.6 1547.32  4938.9 1547.47  4946.8 1546.67  4951.9 1547.13  4969.3 1545.56
  4979.4 1541.46  4989.5 1535.14  4995.3 1532.81  4995.6 1529.81  4999.1 1529.81
  4999.3 1532.81  5007.4 1533.54  5013.0 1534.78  5028.7 1534.61  5050.0 1538.63
  5060.7 1538.01  5068.4 1538.57  5073.7 1539.78  5082.1 1540.82  5092.7 1541.07
  5107.4 1542.20  5135.4 1543.87  5146.1 1544.81  5154.0 1546.13  5159.3 1545.52
  5178.1 1550.95  5184.3 1551.99  5189.6 1551.88  5196.8 1553.77  5199.5 1553.77
#Mann=4,-1,0
  4918.6    0.12       0  4995.3    0.07       0  4999.3    0.12       0
  5107.4    0.05       0
Bank Sta=4995.3,4999.3
Exp/Cntr=0.3,0.1

Type RM Length L Ch R = 1,69060,493,493,493
BEGIN DESCRIPTION:
HONEY CREEK 130.0
END DESCRIPTION:
XS GIS Cut Line= 3
      2827605.67     10201903.12      2827844.25     10201703.00
      2827955.68     10201303.14
#Sta/Elev= 30
  4688.6 1553.42  4691.9 1553.42  4695.8 1551.21  4702.3 1551.91  4730.9 1548.76
  4755.3 1547.61  4831.1 1544.25  4894.6 1540.59  4929.2 1537.13  4950.8 1533.96
  4963.0 1533.01  4963.3 1530.01  4966.8 1530.01  4967.1 1533.01  5041.4 1534.12
  5059.1 1535.28  5064.3 1536.39  5093.3 1537.83  5114.1 1540.26  5147.3 1541.67
  5202.9 1544.88  5211.5 1545.05  5250.9 1548.71  5259.4 1550.14  5285.1 1550.50
  5364.8 1556.82  5373.6 1557.59  5384.0 1559.49  5398.0 1559.89  5415.1 1561.99
#Mann=9,-1,0
  4688.6    0.05       0  4755.3    0.12       0  4894.6    0.05       0
  4929.2    0.12       0  4963.0    0.07       0  4967.1    0.12       0
  5147.3    0.05       0  5202.9    0.12       0  5364.8    0.05       0
Bank Sta=4963,4967.1
Exp/Cntr=0.3,0.1

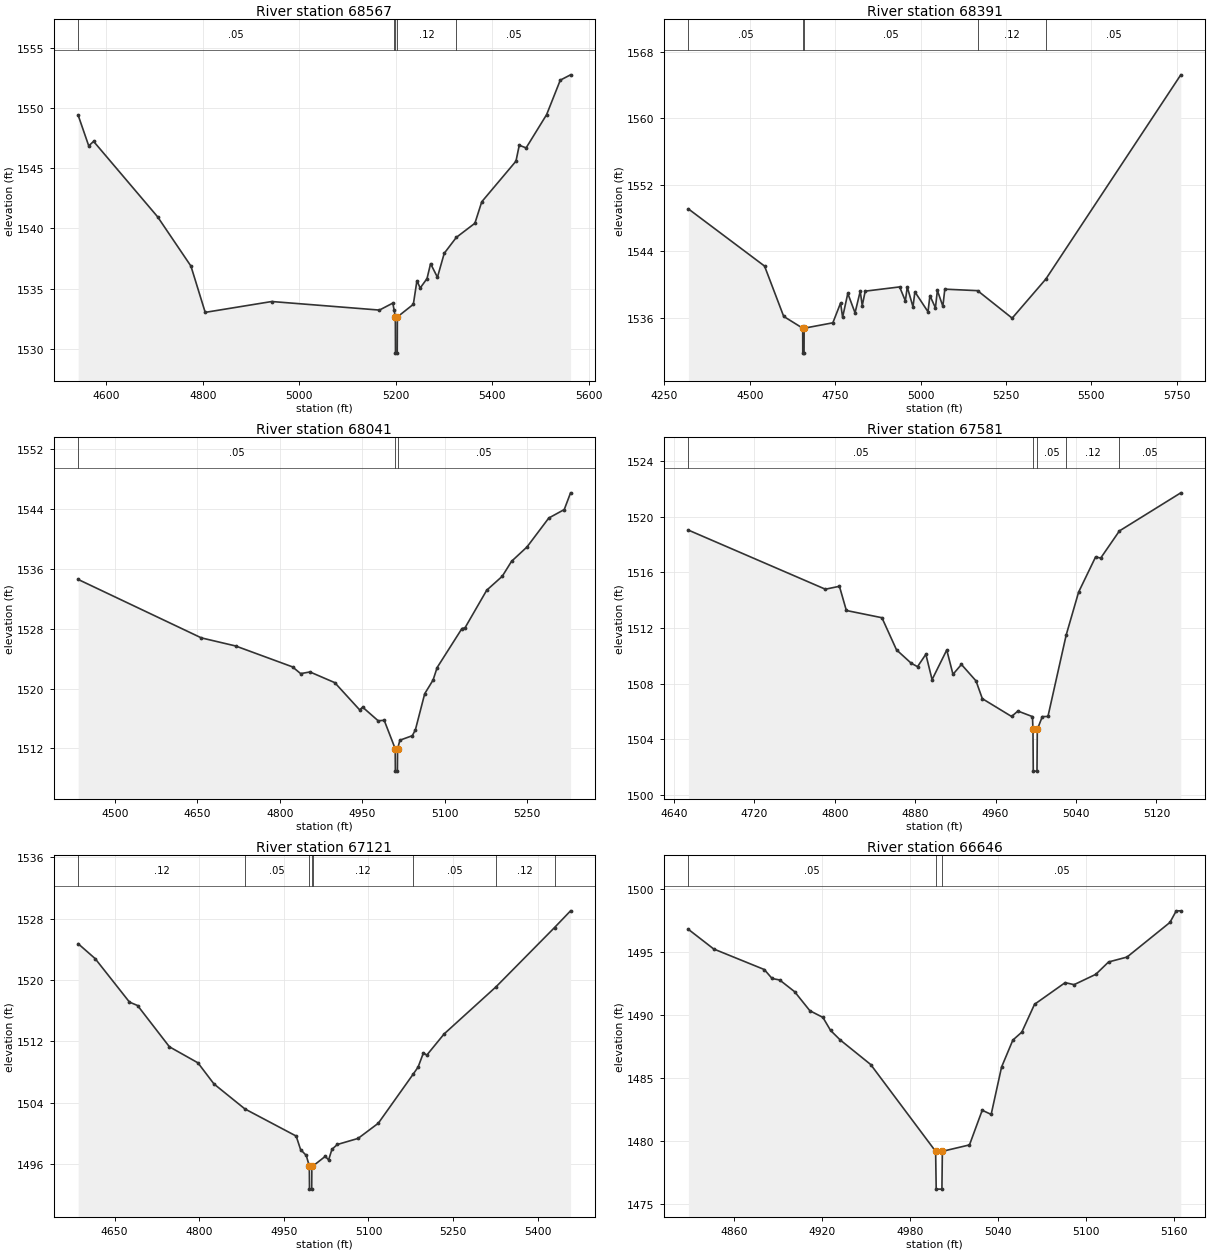
Type RM Length L Ch R = 1,68567,176,176,176
BEGIN DESCRIPTION:
HONEY CREEK 129.0
END DESCRIPTION:
XS GIS Cut Line= 3
      2827805.69     10202203.11      2828223.50     10202015.00
      2828605.69     10201603.10
#Sta/Elev= 30
  4541.8 1549.39  4563.7 1546.85  4573.8 1547.22  4706.3 1540.97  4775.4 1536.88
  4805.0 1533.04  4942.9 1533.94  5165.9 1533.23  5193.7 1533.81  5196.3 1533.24
  5198.9 1532.66  5199.2 1529.66  5202.8 1529.66  5203.1 1532.66  5236.2 1533.71
  5243.6 1535.66  5250.4 1535.06  5264.5 1535.84  5271.9 1537.08  5286.1 1535.95
  5300.2 1537.94  5325.3 1539.26  5363.7 1540.43  5377.9 1542.21  5448.8 1545.58
  5455.6 1546.90  5469.8 1546.68  5512.3 1549.44  5540.6 1552.30  5561.9 1552.74
#Mann=5,-1,0
  4541.8    0.05       0  5196.3    0.12       0  5198.9    0.03       0
  5203.1    0.12       0  5325.3    0.05       0
Bank Sta=5198.9,5203.1
Exp/Cntr=0.3,0.1

Type RM Length L Ch R = 1,68391,350,350,350
BEGIN DESCRIPTION:
Mapping XS f44ec1f5
END DESCRIPTION:
XS GIS Cut Line= 6
      2827909.65     10202599.62      2828132.19     10202316.95
      2828330.65     10202190.66      2828438.90     10201986.18
      2828523.09     10201763.67      2828745.18     10201457.54
#Sta/Elev= 30
  4320.0 1549.10  4543.1 1542.22  4599.2 1536.16  4654.9 1534.74  4655.1 1531.74
  4658.8 1531.74  4659.1 1534.74  4743.2 1535.39  4765.8 1537.77  4771.8 1536.06
  4787.0 1538.93  4808.2 1536.59  4823.4 1539.19  4829.3 1537.46  4838.0 1539.20
  4938.8 1539.71  4955.6 1538.03  4961.2 1539.70  4978.0 1537.31  4983.5 1539.12
  5021.9 1536.72  5027.6 1538.66  5043.7 1537.19  5049.4 1539.29  5065.5 1537.38
  5071.2 1539.44  5167.2 1539.26  5268.5 1535.95  5367.2 1540.66  5762.5 1565.24
#Mann=5,-1,0
  4320.0    0.05       0  4654.9    0.03       0  4659.1    0.05       0
  5167.2    0.12       0  5367.2    0.05       0
Bank Sta=4654.9,4659.1
Exp/Cntr=0.3,0.1

Type RM Length L Ch R = 1,68041,460,460,460
BEGIN DESCRIPTION:
Mapping XS 87bde9f4
END DESCRIPTION:
XS GIS Cut Line= 2
      2828444.90     10202743.96      2828835.82     10201938.06
#Sta/Elev= 30
  4433.3 1534.61  4657.4 1526.79  4719.6 1525.71  4823.2 1522.91  4838.0 1522.01
  4855.0 1522.23  4900.1 1520.80  4945.3 1517.16  4950.8 1517.52  4979.0 1515.70
  4990.0 1515.76  5010.0 1511.96  5010.3 1508.96  5014.0 1508.96  5014.3 1511.96
  5018.6 1513.10  5041.1 1513.70  5046.7 1514.48  5063.7 1519.32  5078.9 1521.15
  5086.3 1522.82  5131.4 1528.04  5137.0 1528.14  5176.5 1533.17  5204.7 1535.03
  5221.7 1537.04  5249.8 1538.96  5289.4 1542.83  5317.5 1543.96  5329.0 1546.20
#Mann=3,-1,0
  4433.3    0.05       0  5010.0    0.05       0  5014.3    0.05       0
Bank Sta=5010,5014.3
Exp/Cntr=0.3,0.1

Type RM Length L Ch R = 1,67581,460,460,460
BEGIN DESCRIPTION:
HONEY CREEK 127.0
END DESCRIPTION:
XS GIS Cut Line= 3
      2828855.70     10202553.10      2829131.75     10202345.00
      2829105.68     10202203.07
#Sta/Elev= 30
  4654.3 1519.04  4790.6 1514.79  4804.6 1515.00  4811.5 1513.26  4846.9 1512.74
  4861.4 1510.43  4876.0 1509.47  4882.3 1509.22  4890.6 1510.11  4896.8 1508.29
  4911.4 1510.42  4917.6 1508.67  4926.0 1509.38  4940.5 1508.20  4946.8 1506.92
  4975.9 1505.64  4982.2 1506.03  4996.7 1505.63  4997.2 1504.71  4997.5 1501.71
  5001.2 1501.71  5001.5 1504.71  5006.5 1505.63  5012.1 1505.64  5030.3 1511.51
  5042.6 1514.58  5059.5 1517.11  5064.6 1517.03  5083.2 1518.98  5144.3 1521.72
#Mann=5,-1,0
  4654.3    0.05       0  4997.2    0.05       0  5001.5    0.05       0
  5030.3    0.12       0  5083.2    0.05       0
Bank Sta=4997.2,5001.5
Exp/Cntr=0.3,0.1

Type RM Length L Ch R = 1,67121,475,475,475
BEGIN DESCRIPTION:
HONEY CREEK 126.0
END DESCRIPTION:
XS GIS Cut Line= 3
      2829605.68     10202903.12      2829546.25     10202493.00
      2829305.70     10202103.14
#Sta/Elev= 30
  4585.6 1524.72  4615.7 1522.78  4676.5 1517.11  4690.9 1516.66  4747.3 1511.28
  4797.8 1509.19  4826.3 1506.43  4881.0 1503.18  4971.9 1499.64  4979.7 1497.88
  4989.8 1497.11  4995.2 1495.72  4995.5 1492.72  4999.4 1492.72  4999.7 1495.72
  5001.4 1495.72  5023.4 1496.99  5029.4 1496.53  5035.3 1497.91  5044.8 1498.54
  5081.5 1499.33  5117.4 1501.31  5178.8 1507.67  5187.9 1508.63  5197.4 1510.49
  5203.3 1510.19  5234.1 1512.96  5326.0 1519.10  5429.7 1526.83  5458.1 1529.01
#Mann=8,-1,0
  4585.6    0.12       0  4881.0    0.05       0  4995.2    0.03       0
  4999.7    0.05       0  5001.4    0.12       0  5178.8    0.05       0
  5326.0    0.12       0  5429.7    0.05       0
Bank Sta=4995.2,4999.7
Exp/Cntr=0.3,0.1

Type RM Length L Ch R = 1,66646,472,472,472
BEGIN DESCRIPTION:
HONEY CREEK 125.0
END DESCRIPTION:
XS GIS Cut Line= 3
      2829955.68     10202553.13      2830000.50     10202388.00
      2829905.67     10202253.09
#Sta/Elev= 30
  4828.9 1496.79  4846.2 1495.23  4880.7 1493.60  4886.0 1492.89  4891.2 1492.77
  4901.4 1491.84  4911.8 1490.33  4920.7 1489.80  4925.9 1488.77  4932.5 1488.01
  4953.3 1486.06  4997.6 1479.17  4998.0 1476.17  5001.9 1476.17  5002.2 1479.17
  5020.7 1479.68  5029.4 1482.43  5035.5 1482.10  5042.6 1485.86  5050.3 1488.00
  5056.4 1488.63  5065.1 1490.84  5086.0 1492.56  5092.1 1492.40  5106.9 1493.22
  5115.6 1494.20  5128.2 1494.59  5157.5 1497.34  5161.8 1498.26  5164.9 1498.26
#Mann=3,-1,0
  4828.9    0.05       0  4997.6    0.05       0  5002.2    0.05       0
Bank Sta=4997.6,5002.2
Exp/Cntr=0.3,0.1