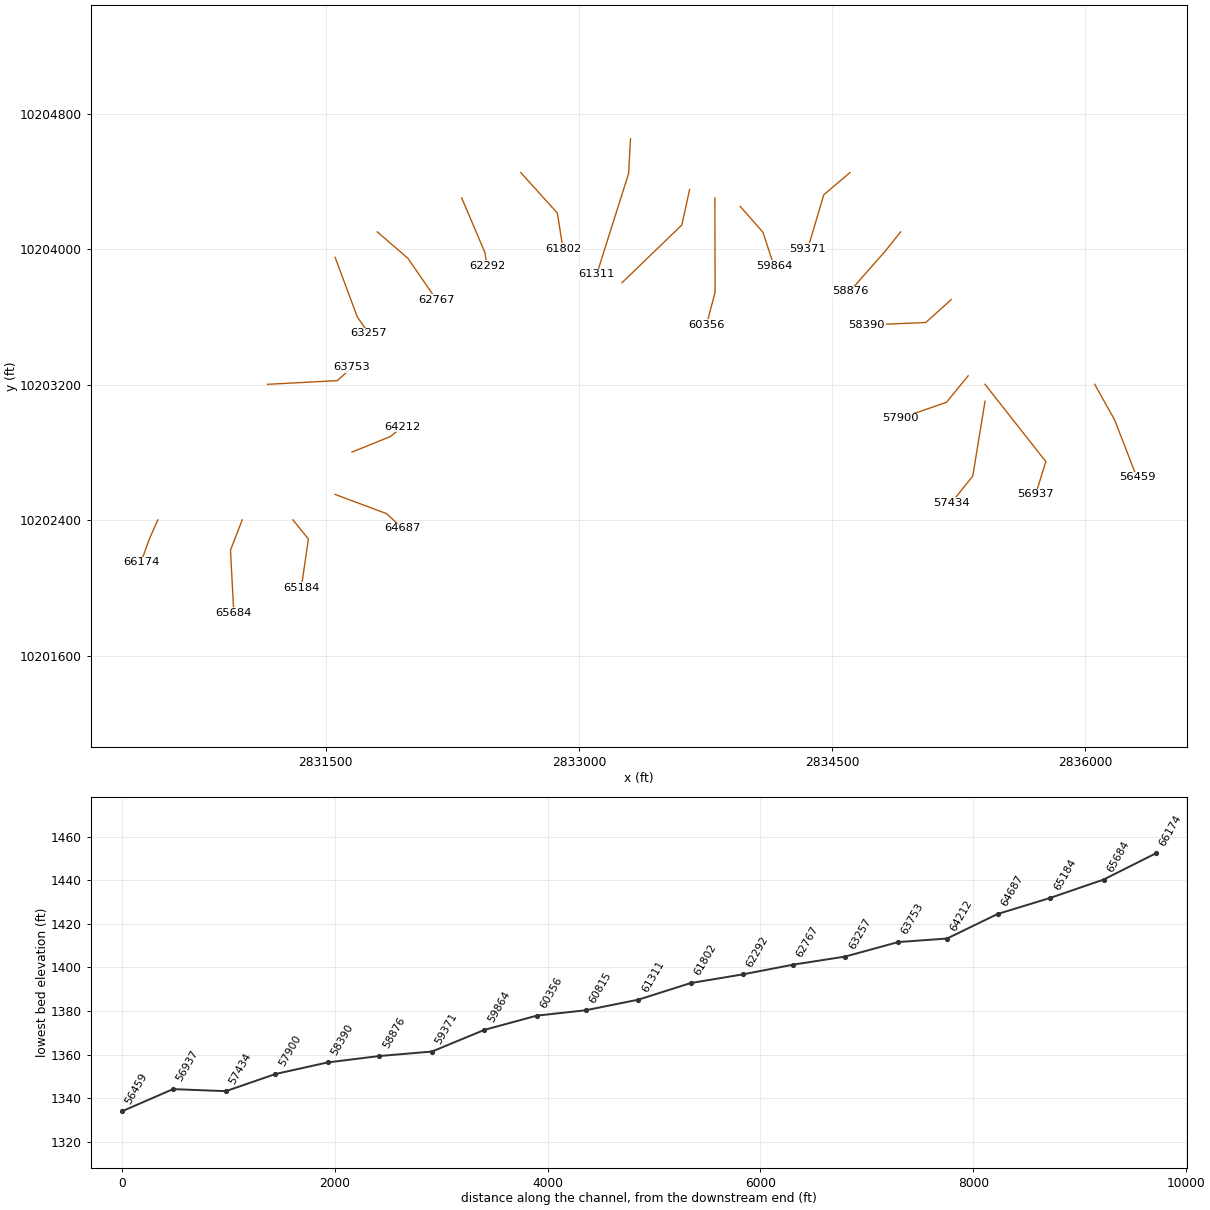
HEC-RAS study HONEY CREEK.prj: HONEY CREEK Base Level Engineering

--- HONEY CREEK.g01 (geometry) --- (continued)

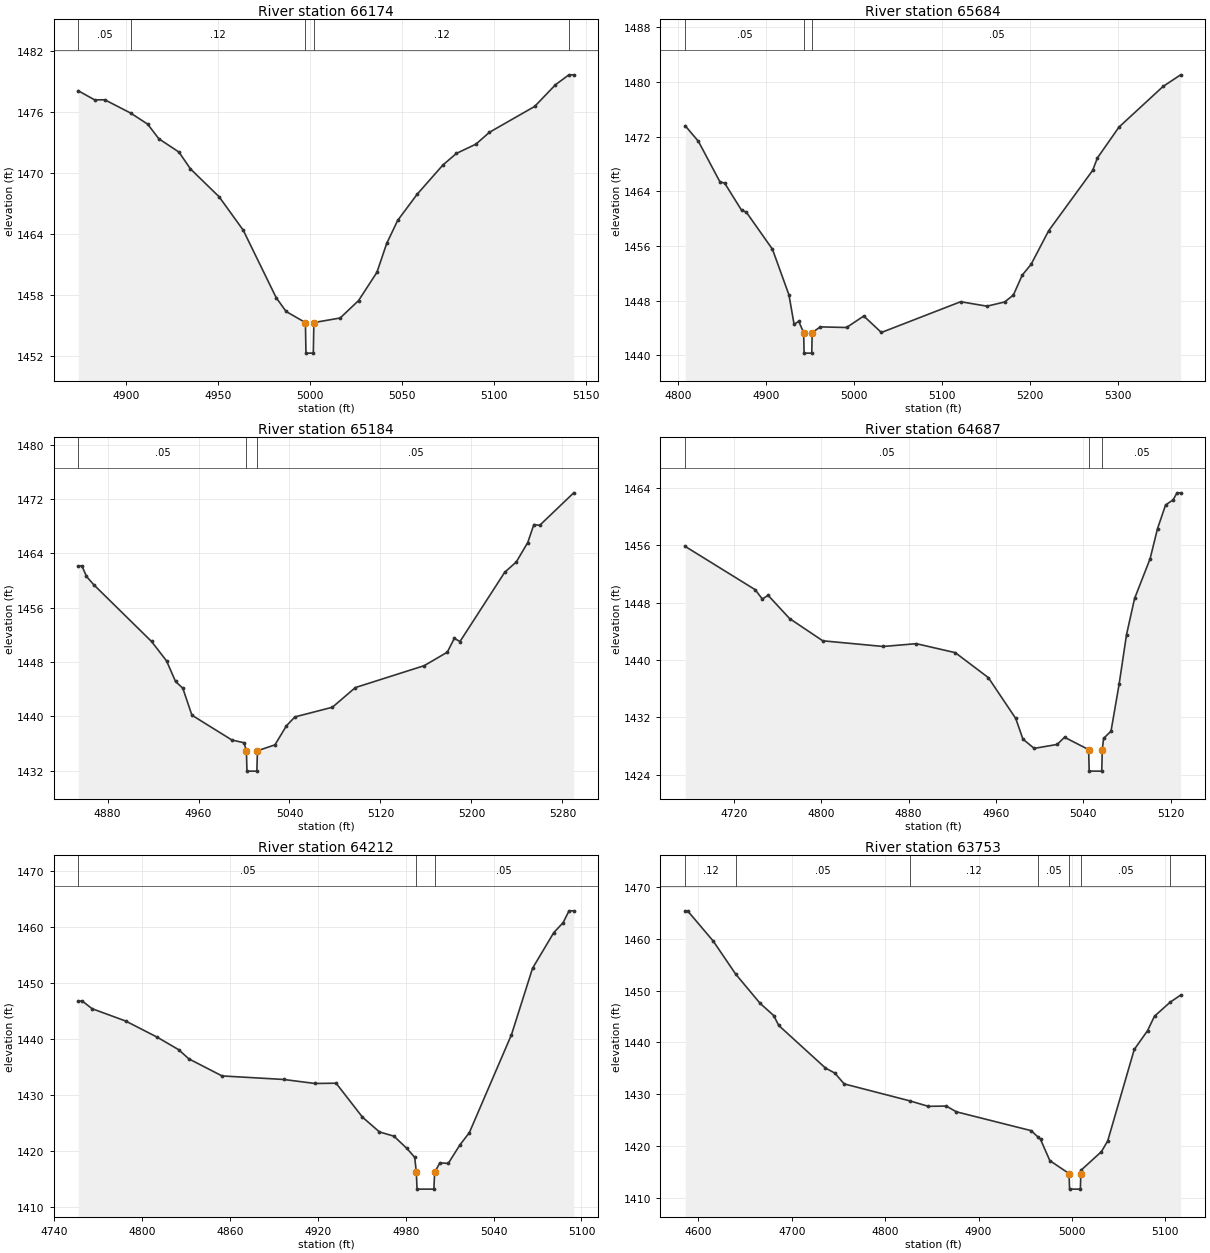
Type RM Length L Ch R = 1,66174,490,490,490
BEGIN DESCRIPTION:
HONEY CREEK 124.0
END DESCRIPTION:
XS GIS Cut Line= 3
      2830505.69     10202403.13      2830454.75     10202288.00
      2830405.70     10202153.14
#Sta/Elev= 30
  4874.1 1478.07  4883.0 1477.18  4888.5 1477.19  4902.5 1475.89  4911.8 1474.80
  4917.9 1473.36  4928.8 1472.06  4935.1 1470.40  4950.7 1467.66  4963.8 1464.38
  4981.7 1457.76  4987.1 1456.40  4997.6 1455.31  4997.9 1452.31  5001.9 1452.31
  5002.2 1455.31  5016.5 1455.76  5026.5 1457.47  5036.5 1460.25  5041.8 1463.08
  5047.8 1465.35  5058.4 1467.92  5072.4 1470.79  5079.7 1471.92  5090.3 1472.83
  5097.7 1474.00  5122.3 1476.54  5133.6 1478.67  5140.9 1479.64  5143.5 1479.64
#Mann=5,-1,0
  4874.1    0.05       0  4902.5    0.12       0  4997.6    0.07       0
  5002.2    0.12       0  5140.9    0.05       0
Bank Sta=4997.6,5002.2
Exp/Cntr=0.3,0.1

Type RM Length L Ch R = 1,65684,500,500,500
BEGIN DESCRIPTION:
HONEY CREEK 123.0
END DESCRIPTION:
XS GIS Cut Line= 3
      2831005.69     10202403.12      2830936.00     10202224.00
      2830955.68     10201853.12
#Sta/Elev= 30
  4807.8 1473.57  4822.8 1471.29  4847.3 1465.36  4852.6 1465.19  4871.8 1461.23
  4877.2 1460.95  4907.0 1455.51  4925.8 1448.82  4931.6 1444.52  4936.9 1444.96
  4942.5 1443.31  4943.0 1440.31  4951.7 1440.31  4952.2 1443.31  4961.4 1444.15
  4991.3 1444.06  5010.9 1445.74  5030.9 1443.33  5121.1 1447.83  5151.1 1447.18
  5171.1 1447.79  5181.1 1448.81  5191.2 1451.73  5201.2 1453.29  5221.2 1458.21
  5271.3 1467.05  5276.7 1468.87  5301.3 1473.39  5351.4 1479.33  5371.4 1481.03
#Mann=3,-1,0
  4807.8    0.05       0  4942.5    0.05       0  4952.2    0.05       0
Bank Sta=4942.5,4952.2
Exp/Cntr=0.3,0.1

Type RM Length L Ch R = 1,65184,497,497,497
BEGIN DESCRIPTION:
HONEY CREEK 122.0
END DESCRIPTION:
XS GIS Cut Line= 3
      2831305.68     10202403.12      2831397.50     10202290.00
      2831355.69     10202003.13
#Sta/Elev= 30
  4854.3 1462.16  4857.5 1462.16  4861.5 1460.60  4867.9 1459.38  4918.7 1451.02
  4931.9 1448.16  4939.8 1445.13  4946.2 1444.13  4954.2 1440.16  4989.4 1436.50
  5000.0 1436.10  5002.1 1434.92  5002.6 1431.92  5011.3 1431.92  5011.8 1434.92
  5027.2 1435.79  5037.3 1438.60  5044.8 1439.91  5077.7 1441.33  5097.9 1444.23
  5158.5 1447.46  5178.8 1449.45  5184.9 1451.48  5189.9 1451.01  5229.3 1461.23
  5239.4 1462.73  5249.5 1465.60  5254.9 1468.25  5260.0 1468.13  5289.9 1472.92
#Mann=3,-1,0
  4854.3    0.05       0  5002.1    0.05       0  5011.8    0.05       0
Bank Sta=5002.1,5011.8
Exp/Cntr=0.3,0.1

Type RM Length L Ch R = 1,64687,475,475,475
BEGIN DESCRIPTION:
HONEY CREEK 121.0
END DESCRIPTION:
XS GIS Cut Line= 3
      2831555.64     10202553.13      2831860.00     10202440.00
      2831955.65     10202353.14
#Sta/Elev= 30
  4675.3 1455.82  4739.4 1449.79  4745.9 1448.49  4751.2 1449.01  4770.9 1445.77
  4801.3 1442.67  4856.6 1441.88  4887.0 1442.27  4922.7 1441.02  4953.0 1437.54
  4978.1 1431.85  4984.7 1428.97  4995.0 1427.68  5016.1 1428.23  5022.8 1429.23
  5044.9 1427.51  5045.4 1424.51  5056.9 1424.51  5057.4 1427.51  5058.6 1429.07
  5065.4 1430.08  5072.8 1436.60  5079.6 1443.52  5087.0 1448.57  5101.2 1454.10
  5108.0 1458.30  5115.4 1461.60  5122.2 1462.30  5125.9 1463.29  5129.2 1463.29
#Mann=3,-1,0
  4675.3    0.05       0  5044.9    0.05       0  5057.4    0.05       0
Bank Sta=5044.9,5057.4
Exp/Cntr=0.3,0.1

Type RM Length L Ch R = 1,64212,459,459,459
BEGIN DESCRIPTION:
HONEY CREEK 120.0
END DESCRIPTION:
XS GIS Cut Line= 3
      2831655.64     10202803.09      2831881.75     10202894.00
      2831955.72     10202953.14
#Sta/Elev= 30
  4756.3 1446.86  4759.0 1446.86  4765.7 1445.49  4788.7 1443.28  4810.2 1440.40
  4824.9 1438.16  4831.8 1436.53  4854.5 1433.48  4896.5 1432.85  4918.0 1432.13
  4932.4 1432.18  4950.4 1426.12  4962.0 1423.48  4971.9 1422.72  4980.8 1420.52
  4986.1 1418.94  4987.2 1416.26  4987.7 1413.26  4999.2 1413.26  4999.7 1416.26
  5003.3 1417.96  5009.0 1417.85  5017.0 1421.17  5023.4 1423.34  5052.2 1440.85
  5066.6 1452.72  5081.1 1459.08  5087.5 1460.87  5091.5 1462.97  5094.7 1462.97
#Mann=3,-1,0
  4756.3    0.05       0  4987.2    0.05       0  4999.7    0.05       0
Bank Sta=4987.2,4999.7
Exp/Cntr=0.3,0.1

Type RM Length L Ch R = 1,63753,496,496,496
BEGIN DESCRIPTION:
HONEY CREEK 119.0
END DESCRIPTION:
XS GIS Cut Line= 3
      2831155.73     10203203.11      2831569.25     10203225.00
      2831655.68     10203303.11
#Sta/Elev= 30
  4585.9 1465.39  4588.4 1465.39  4615.9 1459.54  4640.0 1453.15  4666.0 1447.54
  4680.7 1445.16  4686.0 1443.26  4736.1 1435.03  4746.1 1434.06  4756.1 1431.97
  4826.1 1428.71  4846.2 1427.64  4865.5 1427.69  4876.3 1426.58  4956.4 1422.94
  4963.9 1421.68  4966.4 1421.26  4976.4 1417.16  4997.0 1414.65  4997.5 1411.65
  5009.1 1411.65  5009.6 1414.65  5010.0 1415.33  5031.7 1418.90  5038.4 1420.97
  5066.8 1438.62  5081.0 1442.24  5088.5 1445.05  5105.3 1447.75  5116.5 1449.12
#Mann=7,-1,0
  4585.9    0.12       0  4640.0    0.05       0  4826.1    0.12       0
  4963.9    0.05       0  4997.0    0.05       0  5009.6    0.05       0
  5105.3    0.12       0
Bank Sta=4997,5009.6
Exp/Cntr=0.3,0.1

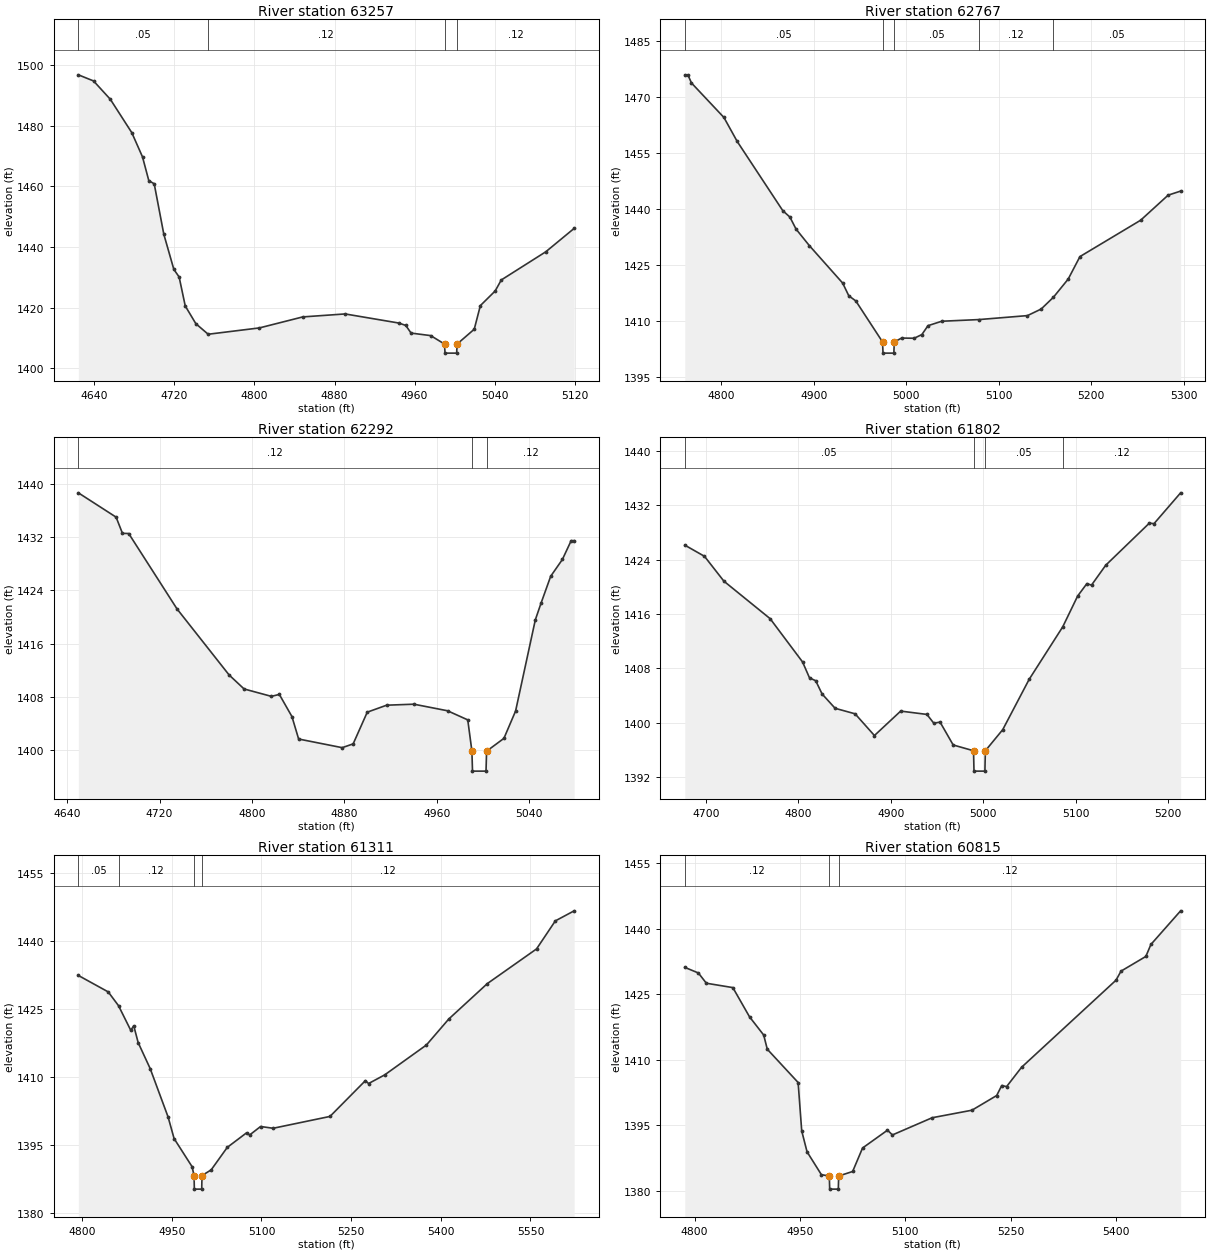
Type RM Length L Ch R = 1,63257,490,490,490
BEGIN DESCRIPTION:
HONEY CREEK 118.0
END DESCRIPTION:
XS GIS Cut Line= 3
      2831555.68     10203953.12      2831687.25     10203601.00
      2831755.66     10203503.14
#Sta/Elev= 30
  4624.1 1496.84  4639.3 1494.82  4656.1 1488.75  4677.5 1477.76  4688.2 1469.76
  4694.5 1461.93  4699.9 1460.88  4709.5 1444.23  4719.5 1432.65  4724.8 1430.13
  4730.9 1420.58  4741.5 1414.72  4753.8 1411.24  4805.0 1413.33  4848.3 1416.96
  4890.6 1417.94  4944.4 1414.93  4951.2 1414.14  4956.5 1411.62  4976.1 1410.79
  4989.9 1408.01  4990.4 1405.01  5002.0 1405.01  5002.5 1408.01  5019.6 1412.90
  5025.7 1420.69  5040.5 1425.52  5046.6 1429.15  5091.1 1438.46  5119.4 1446.17
#Mann=4,-1,0
  4624.1    0.05       0  4753.8    0.12       0  4989.9    0.07       0
  5002.5    0.12       0
Bank Sta=4989.9,5002.5
Exp/Cntr=0.3,0.1

Type RM Length L Ch R = 1,62767,475,475,475
BEGIN DESCRIPTION:
HONEY CREEK 117.0
END DESCRIPTION:
XS GIS Cut Line= 3
      2831805.66     10204103.14      2831987.00     10203947.00
      2832155.66     10203703.14
#Sta/Elev= 30
  4760.7 1475.90  4764.0 1475.90  4767.9 1473.72  4803.0 1464.46  4817.3 1458.05
  4866.6 1439.48  4874.3 1437.76  4880.9 1434.55  4895.2 1430.14  4931.3 1420.07
  4937.9 1416.67  4945.5 1415.28  4974.4 1404.29  4974.9 1401.29  4986.6 1401.29
  4987.1 1404.29  4995.0 1405.33  5008.6 1405.28  5016.9 1406.27  5023.5 1408.65
  5038.4 1409.84  5078.8 1410.29  5131.0 1411.35  5145.8 1413.11  5159.0 1416.26
  5175.0 1421.14  5187.7 1427.17  5253.3 1436.92  5283.0 1443.64  5296.5 1444.73
#Mann=5,-1,0
  4760.7    0.05       0  4974.4    0.05       0  4987.1    0.05       0
  5078.8    0.12       0  5159.0    0.05       0
Bank Sta=4974.4,4987.1
Exp/Cntr=0.3,0.1

Type RM Length L Ch R = 1,62292,490,490,490
BEGIN DESCRIPTION:
HONEY CREEK 116.0
END DESCRIPTION:
XS GIS Cut Line= 3
      2832305.67     10204303.15      2832443.25     10203981.00
      2832455.69     10203903.09
#Sta/Elev= 30
  4649.7 1438.69  4682.4 1435.03  4687.9 1432.59  4693.3 1432.57  4735.1 1421.23
  4780.2 1411.29  4793.2 1409.18  4816.8 1408.07  4823.7 1408.36  4834.6 1405.03
  4840.4 1401.65  4878.1 1400.35  4887.6 1400.92  4899.8 1405.69  4916.6 1406.74
  4940.2 1406.89  4969.3 1405.90  4986.8 1404.53  4990.4 1399.82  4990.9 1396.82
  5002.6 1396.82  5003.1 1399.82  5018.1 1401.75  5028.2 1405.86  5045.3 1419.59
  5050.4 1422.17  5058.6 1426.14  5068.7 1428.66  5076.3 1431.49  5078.9 1431.49
#Mann=3,-1,0
  4649.7    0.12       0  4990.4    0.07       0  5003.1    0.12       0
Bank Sta=4990.4,5003.1
Exp/Cntr=0.3,0.1

Type RM Length L Ch R = 1,61802,491,491,491
BEGIN DESCRIPTION:
HONEY CREEK 115.0
END DESCRIPTION:
XS GIS Cut Line= 3
      2832655.67     10204453.13      2832872.50     10204214.00
      2832905.69     10204003.10
#Sta/Elev= 30
  4677.2 1426.12  4698.5 1424.47  4719.5 1420.81  4769.5 1415.29  4804.6 1408.91
  4812.1 1406.57  4818.8 1406.15  4825.7 1404.20  4839.8 1402.09  4861.4 1401.28
  4882.3 1398.08  4910.7 1401.68  4939.1 1401.19  4946.5 1399.90  4953.3 1400.06
  4967.5 1396.69  4989.5 1395.84  4990.0 1392.84  5001.8 1392.84  5002.3 1395.84
  5021.1 1398.95  5049.6 1406.34  5086.0 1414.09  5102.1 1418.62  5112.1 1420.45
  5117.1 1420.23  5132.5 1423.16  5179.7 1429.36  5184.7 1429.28  5213.5 1433.82
#Mann=4,-1,0
  4677.2    0.05       0  4989.5    0.05       0  5002.3    0.05       0
  5086.0    0.12       0
Bank Sta=4989.5,5002.3
Exp/Cntr=0.3,0.1

Type RM Length L Ch R = 1,61311,496,496,496
BEGIN DESCRIPTION:
HONEY CREEK 114.0
END DESCRIPTION:
XS GIS Cut Line= 3
      2833305.68     10204653.08      2833294.25     10204447.00
      2833105.69     10203853.12
#Sta/Elev= 30
  4793.6 1432.35  4843.6 1428.72  4860.8 1425.69  4881.3 1420.25  4886.3 1421.25
  4893.7 1417.54  4913.8 1411.81  4943.8 1401.13  4953.8 1396.38  4983.9 1390.18
  4987.2 1388.23  4987.7 1385.23  5000.0 1385.23  5000.5 1388.23  5015.8 1389.47
  5042.8 1394.44  5075.1 1397.65  5080.3 1397.18  5098.5 1399.04  5119.5 1398.65
  5214.6 1401.26  5273.9 1409.16  5279.1 1408.51  5306.1 1410.42  5375.9 1417.01
  5413.4 1422.75  5477.9 1430.56  5560.2 1438.20  5591.6 1444.38  5623.1 1446.60
#Mann=4,-1,0
  4793.6    0.05       0  4860.8    0.12       0  4987.2    0.07       0
  5000.5    0.12       0
Bank Sta=4987.2,5000.5
Exp/Cntr=0.3,0.1

Type RM Length L Ch R = 1,60815,459,459,459
BEGIN DESCRIPTION:
HONEY CREEK 113.0
END DESCRIPTION:
XS GIS Cut Line= 3
      2833655.67     10204353.07      2833610.00     10204144.00
      2833255.67     10203803.09
#Sta/Elev= 30
  4786.0 1431.11  4805.3 1429.83  4816.7 1427.48  4854.4 1426.48  4878.1 1419.80
  4898.3 1415.62  4903.4 1412.38  4947.3 1404.76  4952.4 1393.69  4960.0 1388.90
  4980.4 1383.67  4991.7 1383.36  4992.2 1380.36  5004.5 1380.36  5005.0 1383.36
  5024.9 1384.40  5039.0 1389.77  5074.5 1393.85  5081.5 1392.76  5138.1 1396.70
  5194.7 1398.42  5229.9 1401.78  5237.1 1404.07  5244.0 1403.82  5265.4 1408.26
  5399.7 1428.17  5406.9 1430.25  5442.2 1433.61  5449.4 1436.35  5491.7 1444.05
#Mann=3,-1,0
  4786.0    0.12       0  4991.7    0.07       0  5005.0    0.12       0
Bank Sta=4991.7,5005
Exp/Cntr=0.3,0.1

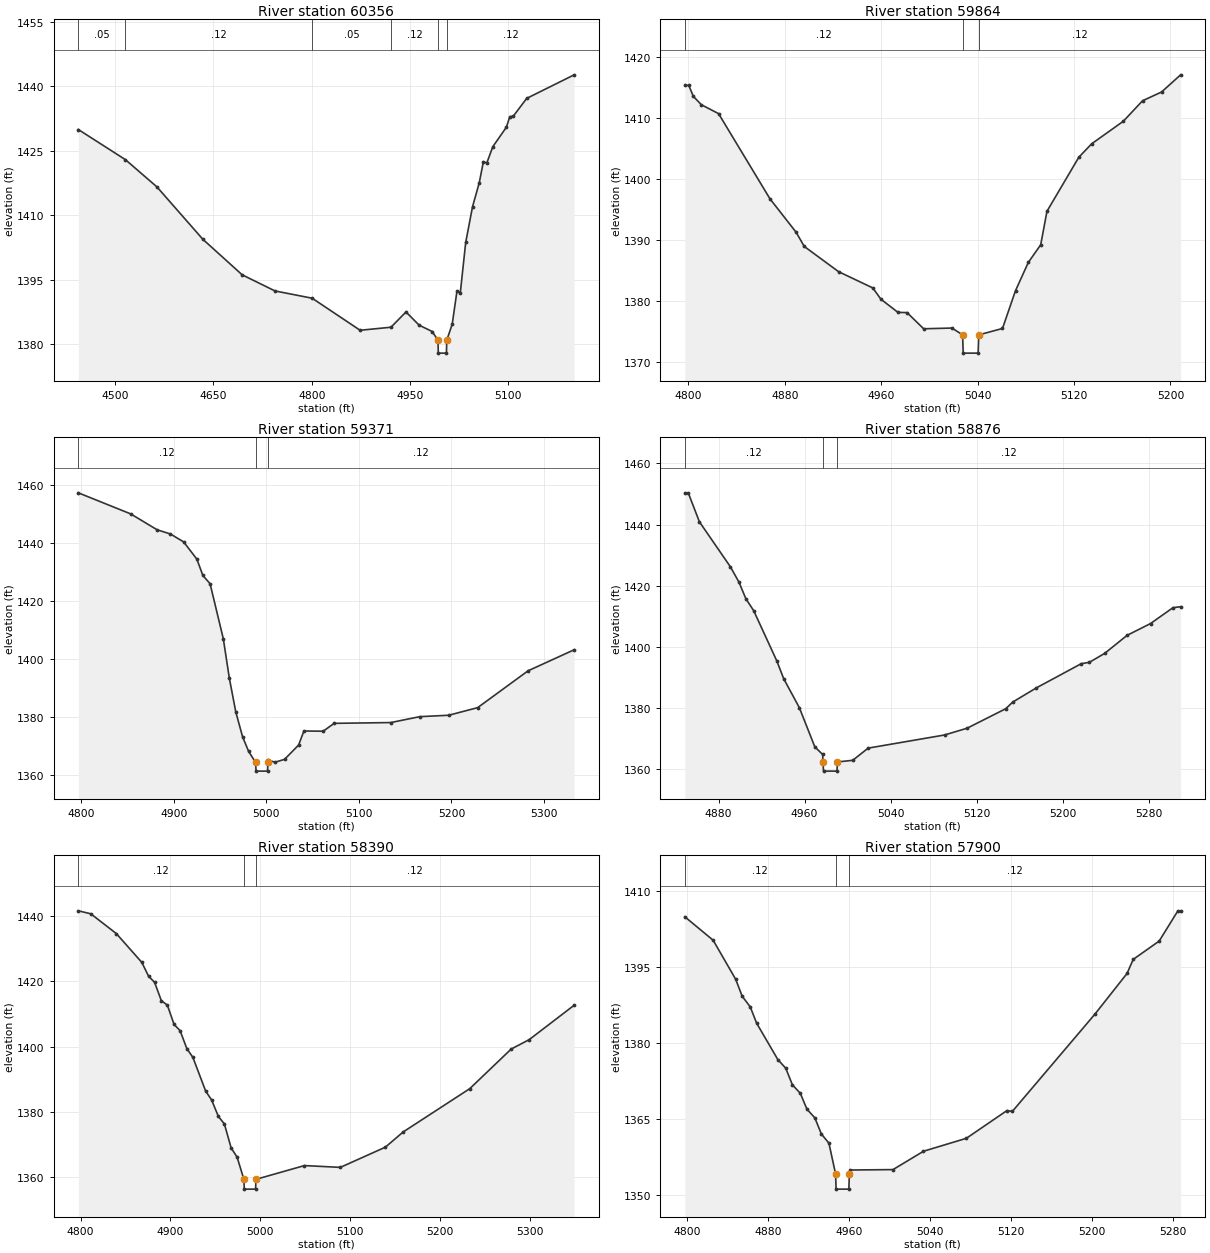
Type RM Length L Ch R = 1,60356,492,492,492
BEGIN DESCRIPTION:
HONEY CREEK 112.0
END DESCRIPTION:
XS GIS Cut Line= 3
      2833805.68     10204303.10      2833806.75     10203747.00
      2833755.68     10203553.11
#Sta/Elev= 30
  4443.9 1429.95  4515.8 1422.93  4563.9 1416.58  4633.9 1404.40  4693.9 1396.13
  4743.9 1392.38  4800.7 1390.68  4873.9 1383.22  4921.0 1383.93  4943.9 1387.49
  4963.9 1384.41  4983.9 1382.93  4992.7 1380.90  4993.2 1377.90  5005.6 1377.90
  5006.1 1380.90  5014.4 1384.62  5021.7 1392.36  5026.8 1391.98  5035.0 1403.66
  5045.4 1411.96  5055.7 1417.57  5062.0 1422.47  5067.2 1422.15  5076.4 1425.96
  5097.1 1430.49  5102.3 1432.94  5107.5 1433.03  5128.1 1437.20  5200.5 1442.68
#Mann=6,-1,0
  4443.9    0.05       0  4515.8    0.12       0  4800.7    0.05       0
  4921.0    0.12       0  4992.7    0.07       0  5006.1    0.12       0
Bank Sta=4992.7,5006.1
Exp/Cntr=0.3,0.1

Type RM Length L Ch R = 1,59864,493,493,493
BEGIN DESCRIPTION:
HONEY CREEK 111.0
END DESCRIPTION:
XS GIS Cut Line= 3
      2833955.70     10204253.09      2834090.00     10204101.00
      2834155.68     10203903.12
#Sta/Elev= 30
  4797.1 1415.36  4800.4 1415.36  4804.2 1413.56  4810.9 1412.18  4825.1 1410.73
  4867.8 1396.72  4889.5 1391.23  4896.2 1388.91  4924.7 1384.76  4953.1 1382.09
  4959.8 1380.24  4974.0 1378.07  4981.5 1378.04  4995.3 1375.38  5018.8 1375.50
  5027.6 1374.38  5028.1 1371.38  5040.5 1371.38  5041.0 1374.38  5060.7 1375.43
  5071.5 1381.64  5082.1 1386.27  5092.4 1389.18  5097.6 1394.68  5124.0 1403.55
  5134.7 1405.77  5161.0 1409.48  5176.9 1412.84  5192.7 1414.28  5208.5 1417.10
#Mann=3,-1,0
  4797.1    0.12       0  5027.6    0.07       0  5041.0    0.12       0
Bank Sta=5027.6,5041
Exp/Cntr=0.3,0.1

Type RM Length L Ch R = 1,59371,495,495,495
BEGIN DESCRIPTION:
HONEY CREEK 110.0
END DESCRIPTION:
XS GIS Cut Line= 3
      2834605.72     10204453.14      2834450.50     10204322.00
      2834355.68     10204003.10
#Sta/Elev= 30
  4796.8 1457.31  4853.4 1450.05  4882.0 1444.57  4896.3 1443.14  4910.6 1440.41
  4924.9 1434.48  4931.4 1428.84  4939.2 1425.99  4953.5 1407.03  4960.0 1393.48
  4967.0 1381.80  4974.3 1373.29  4980.9 1368.21  4988.4 1364.44  4988.9 1361.44
  5001.3 1361.44  5001.8 1364.44  5002.0 1365.27  5009.3 1364.50  5019.7 1365.50
  5034.9 1370.43  5040.6 1375.27  5061.4 1375.19  5073.3 1377.90  5134.5 1378.17
  5165.8 1380.20  5197.1 1380.69  5228.4 1383.31  5282.9 1396.00  5332.7 1403.25
#Mann=3,-1,0
  4796.8    0.12       0  4988.4    0.07       0  5001.8    0.12       0
Bank Sta=4988.4,5001.8
Exp/Cntr=0.3,0.1

Type RM Length L Ch R = 1,58876,486,486,486
BEGIN DESCRIPTION:
HONEY CREEK 109.0
END DESCRIPTION:
XS GIS Cut Line= 3
      2834905.70     10204103.13      2834811.00     10203985.00
      2834605.70     10203753.13
#Sta/Elev= 30
  4848.6 1450.37  4851.8 1450.37  4862.2 1440.89  4891.0 1426.19  4899.0 1421.15
  4905.4 1415.74  4912.7 1411.82  4934.2 1395.38  4940.6 1389.58  4955.1 1380.15
  4969.5 1367.33  4976.8 1364.82  4977.1 1362.38  4977.6 1359.38  4990.1 1359.38
  4990.6 1362.38  5004.8 1362.92  5019.1 1366.90  5090.2 1371.20  5111.1 1373.41
  5147.0 1379.77  5153.7 1381.99  5175.5 1386.59  5217.3 1394.51  5224.8 1394.95
  5239.0 1397.86  5259.9 1403.77  5281.7 1407.63  5302.6 1412.82  5309.7 1413.14
#Mann=3,-1,0
  4848.6    0.12       0  4977.1    0.07       0  4990.6    0.12       0
Bank Sta=4977.1,4990.6
Exp/Cntr=0.3,0.1

Type RM Length L Ch R = 1,58390,490,490,490
BEGIN DESCRIPTION:
HONEY CREEK 108.0
END DESCRIPTION:
XS GIS Cut Line= 3
      2835205.70     10203703.13      2835054.75     10203568.00
      2834705.67     10203553.11
#Sta/Elev= 30
  4797.4 1441.63  4811.2 1440.73  4839.7 1434.67  4868.1 1425.84  4875.6 1421.62
  4882.3 1419.74  4889.8 1414.14  4896.5 1412.76  4904.0 1406.85  4910.7 1404.95
  4918.2 1399.45  4924.9 1396.78  4939.1 1386.49  4945.8 1383.71  4953.3 1378.71
  4960.0 1376.39  4967.5 1369.07  4974.2 1366.20  4981.7 1359.44  4982.2 1356.44
  4994.7 1356.44  4995.2 1359.44  5049.1 1363.65  5089.1 1363.10  5139.2 1369.28
  5159.2 1373.97  5233.2 1387.20  5279.3 1399.32  5299.3 1402.19  5349.4 1412.73
#Mann=3,-1,0
  4797.4    0.12       0  4981.7    0.07       0  4995.2    0.12       0
Bank Sta=4981.7,4995.2
Exp/Cntr=0.3,0.1

Type RM Length L Ch R = 1,57900,466,466,466
BEGIN DESCRIPTION:
HONEY CREEK 107.0
END DESCRIPTION:
XS GIS Cut Line= 3
      2835305.69     10203253.12      2835177.50     10203097.00
      2834905.66     10203003.10
#Sta/Elev= 30
  4798.0 1404.84  4826.0 1400.21  4848.2 1392.53  4854.7 1389.16  4862.6 1387.08
  4869.0 1383.83  4889.9 1376.67  4897.7 1374.97  4904.2 1371.72  4912.1 1370.01
  4918.6 1366.90  4926.4 1365.19  4932.9 1361.99  4940.3 1360.20  4946.9 1354.13
  4947.4 1351.13  4960.0 1351.13  4960.5 1354.13  4961.6 1354.90  5003.6 1354.98
  5033.7 1358.60  5076.0 1361.15  5116.1 1366.62  5121.4 1366.45  5202.9 1385.62
  5234.7 1393.66  5240.8 1396.44  5266.4 1400.04  5284.9 1406.01  5287.6 1406.01
#Mann=3,-1,0
  4798.0    0.12       0  4946.9    0.07       0  4960.5    0.12       0
Bank Sta=4946.9,4960.5
Exp/Cntr=0.3,0.1

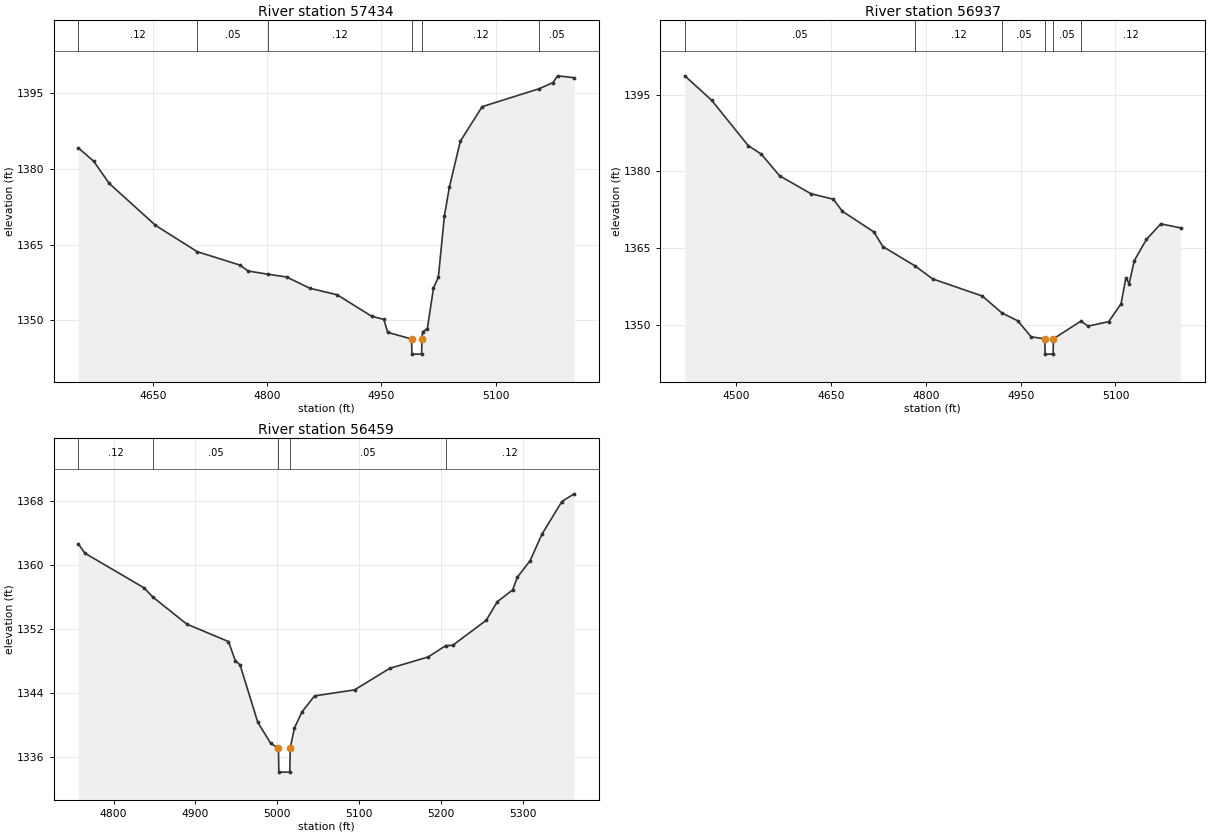
Type RM Length L Ch R = 1,57434,497,497,497
BEGIN DESCRIPTION:
HONEY CREEK 106.0
END DESCRIPTION:
XS GIS Cut Line= 3
      2835405.68     10203103.11      2835333.25     10202661.00
      2835205.67     10202503.10
#Sta/Elev= 30
  4552.0 1384.19  4572.3 1381.52  4592.5 1377.15  4653.3 1368.83  4708.2 1363.59
  4764.1 1360.94  4774.9 1359.76  4801.3 1359.12  4825.4 1358.58  4856.0 1356.34
  4891.8 1355.05  4937.1 1350.79  4953.1 1350.16  4958.2 1347.59  4989.5 1346.27
  4990.0 1343.27  5002.7 1343.27  5003.2 1346.27  5003.9 1347.65  5010.3 1348.35
  5018.3 1356.39  5024.7 1358.53  5032.7 1370.76  5039.1 1376.35  5053.5 1385.50
  5082.2 1392.37  5156.9 1395.92  5175.0 1397.13  5181.4 1398.49  5203.0 1398.11
#Mann=6,-1,0
  4552.0    0.12       0  4708.2    0.05       0  4801.3    0.12       0
  4989.5    0.07       0  5003.2    0.12       0  5156.9    0.05       0
Bank Sta=4989.5,5003.2
Exp/Cntr=0.3,0.1

Type RM Length L Ch R = 1,56937,478,478,478
BEGIN DESCRIPTION:
HONEY CREEK 105.0
END DESCRIPTION:
XS GIS Cut Line= 3
      2835405.66     10203203.14      2835766.00     10202747.00
      2835705.67     10202553.07
#Sta/Elev= 30
  4418.7 1398.75  4461.2 1393.96  4519.0 1385.07  4539.8 1383.40  4568.6 1379.16
  4618.3 1375.64  4653.6 1374.57  4668.0 1372.20  4717.7 1368.16  4732.1 1365.28
  4783.0 1361.49  4810.7 1358.95  4889.3 1355.59  4920.5 1352.26  4945.3 1350.74
  4966.7 1347.59  4988.2 1347.20  4988.7 1344.20  5001.4 1344.20  5001.9 1347.20
  5045.3 1350.67  5056.6 1349.69  5089.2 1350.56  5108.8 1354.04  5116.5 1359.12
  5121.7 1358.03  5129.7 1362.50  5149.0 1366.68  5171.6 1369.74  5203.1 1368.94
#Mann=6,-1,0
  4418.7    0.05       0  4783.0    0.12       0  4920.5    0.05       0
  4988.2    0.05       0  5001.9    0.05       0  5045.3    0.12       0
Bank Sta=4988.2,5001.9
Exp/Cntr=0.3,0.1

Type RM Length L Ch R = 1,56459,459,459,459
BEGIN DESCRIPTION:
HONEY CREEK 104.0
END DESCRIPTION:
XS GIS Cut Line= 3
      2836055.70     10203203.09      2836174.50     10202991.00
      2836305.70     10202653.08
#Sta/Elev= 30
  4756.9 1362.59  4764.9 1361.43  4837.1 1357.10  4848.0 1355.94  4889.3 1352.57
  4940.3 1350.38  4948.6 1348.00  4954.4 1347.47  4976.1 1340.28  4992.0 1337.64
  5001.3 1337.06  5001.8 1334.06  5015.2 1334.06  5015.7 1337.06  5020.8 1339.56
  5029.9 1341.56  5045.4 1343.59  5094.3 1344.34  5137.2 1347.03  5184.2 1348.46
  5205.8 1349.88  5214.1 1349.91  5255.2 1353.05  5268.5 1355.35  5287.4 1356.84
  5293.1 1358.42  5308.8 1360.51  5323.0 1363.77  5347.5 1367.89  5362.5 1368.85
#Mann=5,-1,0
  4756.9    0.12       0  4848.0    0.05       0  5001.3    0.05       0
  5015.7    0.05       0  5205.8    0.12       0
Bank Sta=5001.3,5015.7
Exp/Cntr=0.3,0.1