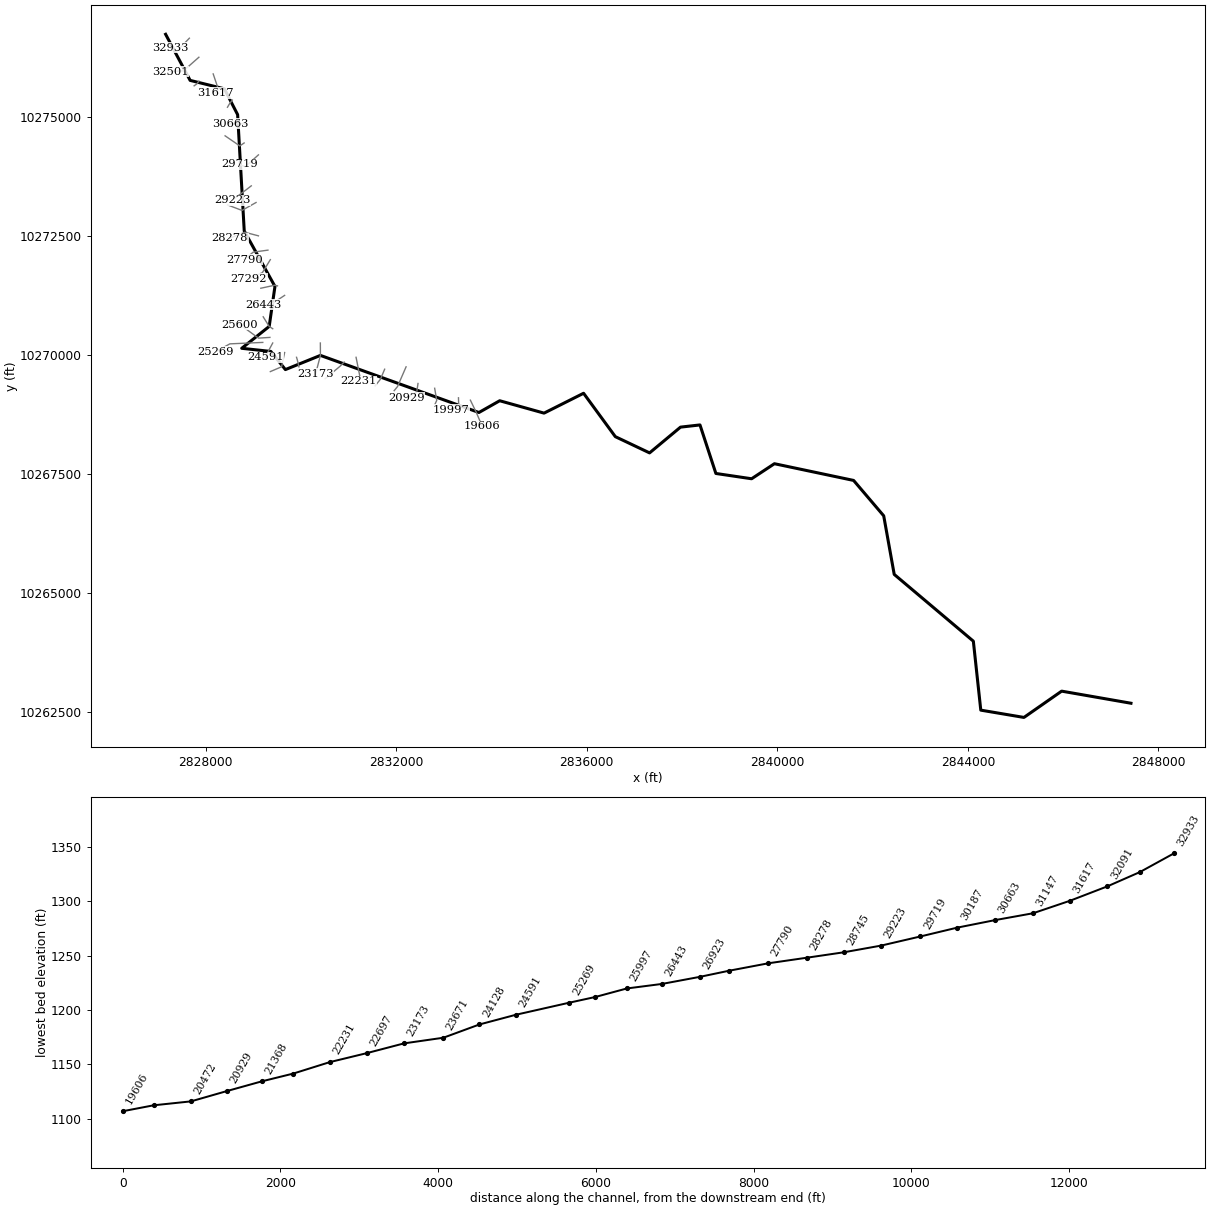
--- REED CREEK.prj (project) ---

Proj Title=REED CREEK Base Level Engineering
Current Plan=p01
Default Exp/Contr=0.3,0.1
English Units
Geom File=g01
Flow File=f01
Plan File=p01
Y Axis Title=Elevation
X Axis Title(PF)=Main Channel Distance
X Axis Title(XS)=Station
BEGIN DESCRIPTION:
REED CREEK
END DESCRIPTION:
DSS Export Rating Curves= 0
DSS Export Rating Curve Sorted= 0
DSS Export Volume Flow Curves= 0
DXF OffsetX= 0
DXF OffsetY= 0
DXF ScaleX= 1
DXF ScaleY= 10

--- REED CREEK.p01 (plan) ---

Plan Title=Multiple Run
Short Identifier=Multiple
Geom File=g01
Flow File=f01
Subcritical Flow
K Sum by GR= 0
Std Step Tol= 0.01
Critical Tol= 0.01
Num of Std Step Trials= 20
Max Error Tol= 0.3
Flow Tol Ratio= 0.001
Split Flow NTrial= 30
Split Flow Tol= 0.02
Split Flow Ratio= 0.02
Log Output Level= 0
Friction Slope Method= 1
Unsteady Friction Slope Method= 2
Unsteady Bridges Friction Slope Method= 1
Parabolic Critical Depth
Global Vel Dist=  1 , 1 , 1
Global Log Level= 0
CheckData=True
Encroach Param= -1, 0, 0, 0
BEGIN DESCRIPTION:
Multiple Run
END DESCRIPTION:

--- REED CREEK.f01 (steady flow) ---

Flow Title=Multiple
Program Version=4.10
Number of Profiles= 7
Profile Names=10-year,25-year,50-year,1pct_min,100-year,1pct_plu,500-year
River Rch & RM=REED CREEK,Reach-1         ,32933
      67     127     197     102     307     927     805
River Rch & RM=REED CREEK,Reach-1         ,23173
      94     186     296     156     471    1423    1277
River Rch & RM=REED CREEK,Reach-1         ,16772
     131     273     443     237     716    2162    1996
River Rch & RM=REED CREEK,Reach-1         ,12092
     134     280     455     244     736    2223    2056
River Rch & RM=REED CREEK,Reach-1         ,11098
     220     483     804     439    1327    4006    3838
River Rch & RM=REED CREEK,Reach-1         ,4410
     222     490     816     446    1348    4071    3904
River Rch & RM=REED CREEK,Reach-1         ,3464
     329     744    1258     696    2103    6351    6232
Boundary for River Rch & Prof#=REED CREEK,Reach-1         , 1
Up Type= 0
Dn Type= 3
Dn Slope=0.0005
Boundary for River Rch & Prof#=REED CREEK,Reach-1         , 2
Up Type= 0
Dn Type= 3
Dn Slope=0.0005
Boundary for River Rch & Prof#=REED CREEK,Reach-1         , 3
Up Type= 0
Dn Type= 3
Dn Slope=0.0005
Boundary for River Rch & Prof#=REED CREEK,Reach-1         , 4
Up Type= 0
Dn Type= 3
Dn Slope=0.0005
Boundary for River Rch & Prof#=REED CREEK,Reach-1         , 5
Up Type= 0
Dn Type= 3
Dn Slope=0.0005
Boundary for River Rch & Prof#=REED CREEK,Reach-1         , 6
Up Type= 0
Dn Type= 3
Dn Slope=0.0005
Boundary for River Rch & Prof#=REED CREEK,Reach-1         , 7
Up Type= 0
Dn Type= 3
Dn Slope=0.0005
DSS Import GetInterval= 0
DSS Import GetPeak= 0
DSS Import FillOption= 0

--- REED CREEK.g01 (geometry) ---

Geom Title=Existing Conditions

River Reach=REED CREEK,Reach-1
Reach XY= 30
      2827157.00     10276735.00      2827671.75     10275767.00
      2828390.50     10275590.00      2828668.75     10275048.00
      2828807.75     10272605.00      2829452.50     10271441.00
      2829331.50     10270601.00      2828755.00     10270142.00
      2829366.25     10270076.00      2829671.75     10269695.00
      2830407.25     10269993.00      2833735.00     10268794.00
      2834171.25     10269041.00      2835102.25     10268781.00
      2835932.25     10269198.00      2836598.75     10268287.00
      2837317.75     10267946.00      2837967.50     10268487.00
      2838376.25     10268533.00      2838710.00     10267514.00
      2839460.00     10267403.00      2839939.00     10267719.00
      2841601.50     10267368.00      2842233.50     10266625.00
      2842454.25     10265395.00      2844115.50     10263993.00
      2844271.75     10262545.00      2845178.00     10262392.00
      2845969.50     10262944.00      2847424.75     10262690.00

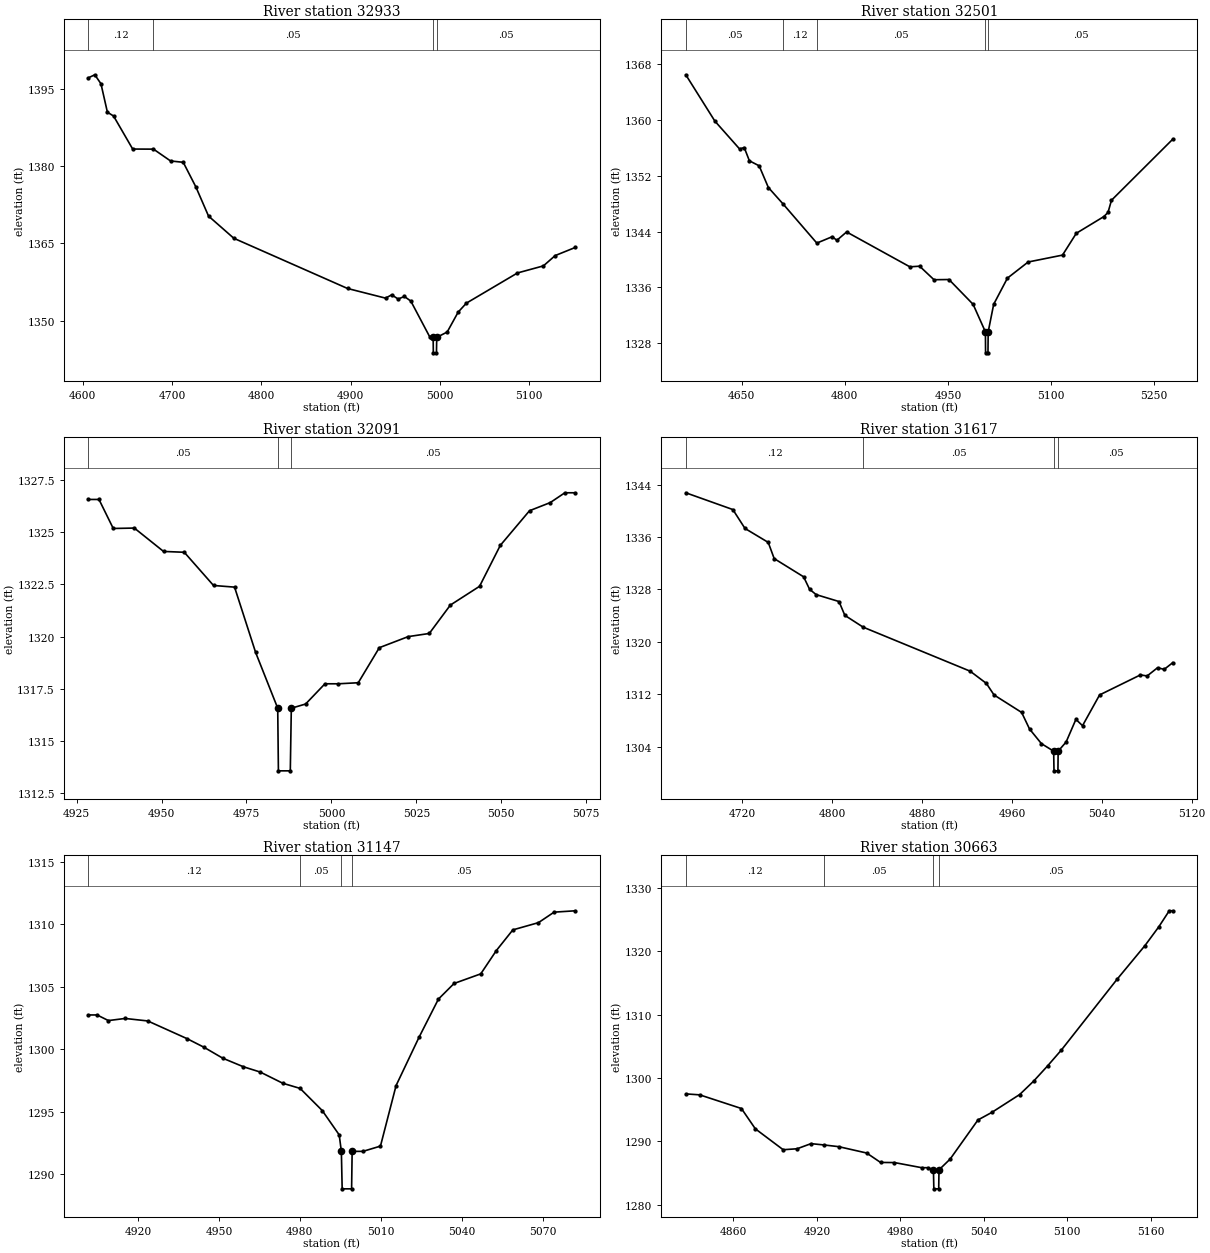
Type RM Length L Ch R = 1,32933,432,432,432
BEGIN DESCRIPTION:
REED CREEK 68.0
END DESCRIPTION:
XS GIS Cut Line= 3
      2827655.67     10276653.09      2827382.50     10276370.00
      2827255.70     10276453.10
#Sta/Elev= 30
  4606.6 1397.10  4613.7 1397.68  4620.6 1395.94  4627.8 1390.43  4634.7 1389.69
  4656.1 1383.29  4679.4 1383.27  4698.5 1380.98  4712.7 1380.72  4726.8 1375.96
  4741.0 1370.30  4769.3 1366.00  4896.6 1356.27  4939.1 1354.40  4946.0 1355.04
  4953.2 1354.23  4960.2 1354.72  4967.4 1353.83  4988.5 1346.92  4992.4 1346.80
  4992.6 1343.80  4996.1 1343.80  4996.4 1346.80  5008.1 1347.83  5020.4 1351.69
  5029.6 1353.43  5086.8 1359.28  5115.8 1360.65  5129.0 1362.65  5151.6 1364.23
#Mann=4,-1,0
  4606.6    0.12       0  4679.4    0.05       0  4992.4    0.05       0
  4996.4    0.05       0
Bank Sta=4992.4,4996.4
Exp/Cntr=0.3,0.1

Type RM Length L Ch R = 1,32501,410,410,410
BEGIN DESCRIPTION:
REED CREEK 67.0
END DESCRIPTION:
XS GIS Cut Line= 3
      2827855.71     10276253.14      2827532.25     10275968.00
      2827255.65     10275953.11
#Sta/Elev= 30
  4568.8 1366.48  4611.1 1359.84  4647.1 1355.84  4653.8 1356.05  4661.3 1354.15
  4675.5 1353.43  4688.9 1350.32  4710.3 1347.96  4759.4 1342.35  4781.8 1343.27
  4788.5 1342.75  4802.7 1343.95  4894.7 1338.95  4908.9 1339.04  4929.8 1337.10
  4951.6 1337.13  4986.7 1333.57  5004.6 1329.62  5004.8 1326.62  5008.3 1326.62
  5008.6 1329.62  5016.6 1333.58  5036.6 1337.33  5066.7 1339.64  5116.7 1340.63
  5136.8 1343.76  5176.8 1346.15  5182.9 1346.75  5187.9 1348.49  5277.0 1357.24
#Mann=5,-1,0
  4568.8    0.05       0  4710.3    0.12       0  4759.4    0.05       0
  5004.6    0.05       0  5008.6    0.05       0
Bank Sta=5004.6,5008.6
Exp/Cntr=0.3,0.1

Type RM Length L Ch R = 1,32091,474,474,474
BEGIN DESCRIPTION:
REED CREEK 66.0
END DESCRIPTION:
XS GIS Cut Line= 3
      2827855.67     10275753.10      2827814.00     10275695.00
      2827755.68     10275653.11
#Sta/Elev= 27
  4928.5 1326.57  4931.6 1326.57  4935.8 1325.18  4942.0 1325.20  4950.6 1324.08
  4956.7 1324.04  4965.3 1322.45  4971.5 1322.37  4977.7 1319.24  4984.2 1316.57
  4984.4 1313.57  4987.9 1313.57  4988.2 1316.57  4992.4 1316.77  4998.1 1317.74
  5002.0 1317.74  5007.9 1317.79  5014.1 1319.47  5022.6 1320.00  5028.8 1320.15
  5035.0 1321.51  5043.6 1322.41  5049.7 1324.37  5058.3 1326.03  5064.4 1326.42
  5068.7 1326.89  5071.8 1326.89
#Mann=3,-1,0
  4928.5    0.05       0  4984.2    0.05       0  4988.2    0.05       0
Bank Sta=4984.2,4988.2
Exp/Cntr=0.3,0.1

Type RM Length L Ch R = 1,31617,470,470,470
BEGIN DESCRIPTION:
REED CREEK 65.0
END DESCRIPTION:
XS GIS Cut Line= 3
      2828155.69     10275903.08      2828261.25     10275590.00
      2828205.70     10275503.14
#Sta/Elev= 30
  4669.6 1342.75  4711.5 1340.19  4722.3 1337.31  4743.0 1335.18  4748.3 1332.71
  4774.5 1329.93  4779.8 1328.03  4785.7 1327.21  4806.0 1326.16  4811.2 1324.05
  4827.5 1322.25  4922.8 1315.53  4937.2 1313.67  4944.0 1311.91  4968.6 1309.24
  4975.6 1306.72  4986.2 1304.48  4997.1 1303.33  4997.4 1300.33  5000.9 1300.33
  5001.1 1303.33  5008.2 1304.73  5016.9 1308.18  5022.8 1307.22  5038.0 1311.91
  5074.4 1314.97  5080.3 1314.80  5089.6 1316.06  5095.5 1315.81  5103.1 1316.83
#Mann=4,-1,0
  4669.6    0.12       0  4827.5    0.05       0  4997.1    0.05       0
  5001.1    0.05       0
Bank Sta=4997.1,5001.1
Exp/Cntr=0.3,0.1

Type RM Length L Ch R = 1,31147,484,484,484
BEGIN DESCRIPTION:
REED CREEK 64.0
END DESCRIPTION:
XS GIS Cut Line= 3
      2828555.71     10275353.15      2828497.25     10275274.00
      2828455.67     10275203.09
#Sta/Elev= 30
  4901.6 1302.73  4904.8 1302.73  4909.0 1302.28  4915.2 1302.45  4923.6 1302.25
  4938.2 1300.83  4944.4 1300.15  4951.4 1299.27  4959.1 1298.58  4965.3 1298.16
  4973.7 1297.26  4980.1 1296.85  4988.3 1295.08  4994.6 1293.13  4995.4 1291.81
  4995.7 1288.81  4999.2 1288.81  4999.4 1291.81  5003.4 1291.81  5009.9 1292.23
  5015.7 1297.08  5024.2 1300.94  5031.4 1304.00  5037.2 1305.25  5047.1 1306.02
  5052.9 1307.89  5059.0 1309.54  5068.5 1310.12  5074.3 1310.96  5082.2 1311.07
#Mann=4,-1,0
  4901.6    0.12       0  4980.1    0.05       0  4995.4    0.05       0
  4999.4    0.05       0
Bank Sta=4995.4,4999.4
Exp/Cntr=0.3,0.1

Type RM Length L Ch R = 1,30663,476,476,476
BEGIN DESCRIPTION:
REED CREEK 63.0
END DESCRIPTION:
XS GIS Cut Line= 3
      2828855.68     10274853.11      2828681.50     10274856.00
      2828505.72     10274853.11
#Sta/Elev= 30
  4825.8 1297.48  4835.8 1297.33  4865.8 1295.17  4875.8 1291.96  4895.8 1288.66
  4905.8 1288.81  4915.8 1289.62  4925.3 1289.41  4935.8 1289.14  4955.8 1288.14
  4965.8 1286.65  4975.8 1286.63  4995.4 1285.82  5000.0 1285.82  5003.8 1285.48
  5004.1 1282.48  5007.6 1282.48  5007.8 1285.48  5015.8 1287.18  5035.8 1293.36
  5045.8 1294.56  5065.8 1297.38  5075.8 1299.49  5085.8 1301.89  5095.8 1304.42
  5135.8 1315.59  5155.8 1320.90  5165.8 1323.88  5173.3 1326.41  5175.8 1326.41
#Mann=4,-1,0
  4825.8    0.12       0  4925.3    0.05       0  5003.8    0.05       0
  5007.8    0.05       0
Bank Sta=5003.8,5007.8
Exp/Cntr=0.3,0.1

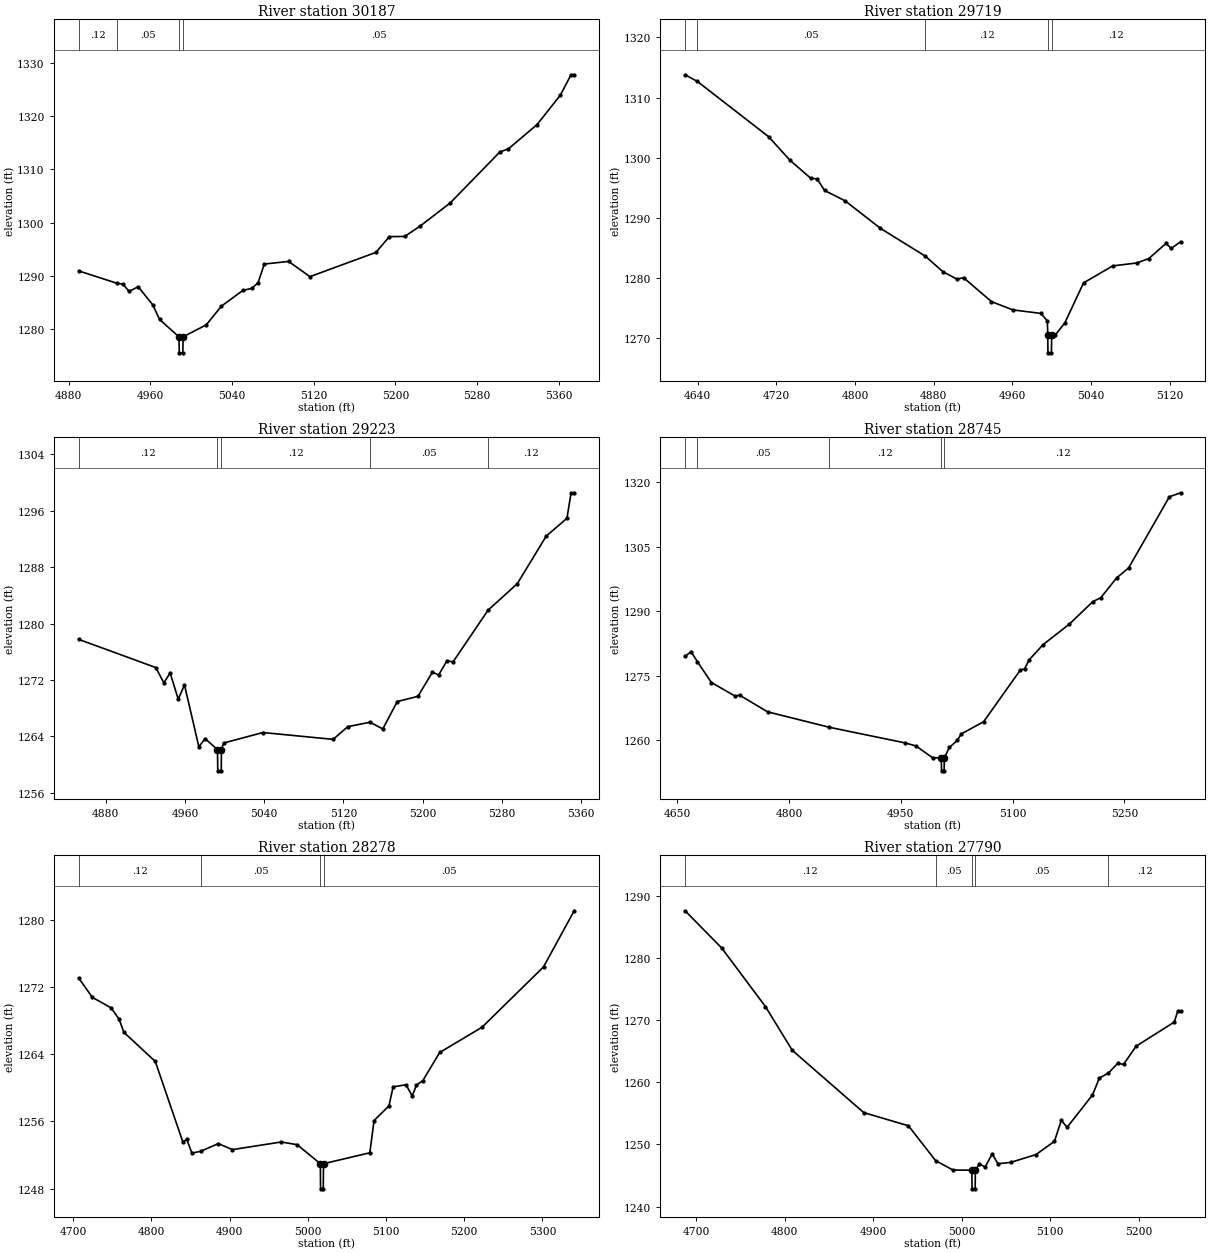
Type RM Length L Ch R = 1,30187,468,468,468
BEGIN DESCRIPTION:
REED CREEK 62.0
END DESCRIPTION:
XS GIS Cut Line= 3
      2828805.67     10274453.10      2828714.75     10274391.00
      2828405.64     10274603.14
#Sta/Elev= 30
  4889.9 1290.98  4927.7 1288.64  4933.2 1288.51  4939.3 1287.13  4948.2 1288.01
  4962.5 1284.60  4969.1 1281.88  4988.1 1278.62  4988.4 1275.62  4991.9 1275.62
  4992.1 1278.62  5014.8 1280.86  5029.7 1284.38  5050.7 1287.32  5059.5 1287.71
  5065.6 1288.79  5071.6 1292.26  5095.4 1292.75  5116.3 1289.90  5180.8 1294.44
  5194.1 1297.40  5209.0 1297.43  5223.9 1299.34  5253.6 1303.71  5302.1 1313.25
  5310.6 1313.86  5338.5 1318.38  5361.3 1323.89  5371.8 1327.73  5374.9 1327.73
#Mann=4,-1,0
  4889.9    0.12       0  4927.7    0.05       0  4988.1    0.05       0
  4992.1    0.05       0
Bank Sta=4988.1,4992.1
Exp/Cntr=0.3,0.1

Type RM Length L Ch R = 1,29719,496,496,496
BEGIN DESCRIPTION:
REED CREEK 61.0
END DESCRIPTION:
XS GIS Cut Line= 3
      2829105.72     10274203.14      2828827.50     10273955.00
      2828705.66     10274003.12
#Sta/Elev= 30
  4627.2 1313.79  4639.6 1312.69  4712.1 1303.48  4733.8 1299.56  4754.7 1296.59
  4761.4 1296.44  4769.0 1294.53  4789.9 1292.80  4825.8 1288.22  4871.4 1283.59
  4889.3 1281.00  4903.6 1279.76  4910.3 1280.00  4938.7 1276.02  4960.4 1274.64
  4988.8 1274.06  4995.5 1272.81  4995.9 1270.49  4996.1 1267.49  4999.6 1267.49
  4999.9 1270.49  5003.7 1270.49  5013.3 1272.49  5032.3 1279.14  5062.0 1281.97
  5086.4 1282.45  5098.7 1283.19  5116.1 1285.71  5121.5 1284.87  5131.0 1286.00
#Mann=5,-1,0
  4627.2    0.12       0  4639.6    0.05       0  4871.4    0.12       0
  4995.9    0.07       0  4999.9    0.12       0
Bank Sta=4995.9,4999.9
Exp/Cntr=0.3,0.1

Type RM Length L Ch R = 1,29223,478,478,478
BEGIN DESCRIPTION:
REED CREEK 60.0
END DESCRIPTION:
XS GIS Cut Line= 3
      2828955.66     10273553.09      2828839.25     10273463.00
      2828555.68     10273253.11
#Sta/Elev= 30
  4852.8 1277.77  4930.6 1273.77  4938.8 1271.60  4945.1 1273.01  4953.3 1269.29
  4959.6 1271.31  4974.1 1262.54  4980.4 1263.69  4992.9 1262.13  4993.2 1259.13
  4996.7 1259.13  4996.9 1262.13  4999.1 1263.07  5038.7 1264.56  5109.6 1263.59
  5124.3 1265.39  5146.8 1266.02  5159.7 1265.07  5174.3 1268.95  5195.2 1269.69
  5209.8 1273.12  5216.0 1272.72  5224.4 1274.71  5230.7 1274.59  5265.9 1281.90
  5295.4 1285.65  5324.6 1292.40  5345.5 1294.92  5349.7 1298.54  5352.8 1298.54
#Mann=5,-1,0
  4852.8    0.12       0  4992.9    0.07       0  4996.9    0.12       0
  5146.8    0.05       0  5265.9    0.12       0
Bank Sta=4992.9,4996.9
Exp/Cntr=0.3,0.1

Type RM Length L Ch R = 1,28745,467,467,467
BEGIN DESCRIPTION:
REED CREEK 59.0
END DESCRIPTION:
XS GIS Cut Line= 3
      2829055.71     10273203.13      2828759.75     10273037.00
      2828455.67     10273153.12
#Sta/Elev= 30
  4660.6 1279.53  4668.6 1280.62  4676.9 1278.32  4696.0 1273.43  4727.9 1270.26
  4733.7 1270.50  4771.3 1266.63  4854.1 1263.04  4955.0 1259.44  4970.3 1258.71
  4992.6 1255.97  5004.4 1255.92  5004.7 1252.92  5008.2 1252.92  5008.4 1255.92
  5015.1 1258.35  5025.8 1259.98  5031.1 1261.49  5061.2 1264.34  5110.6 1276.39
  5116.0 1276.57  5122.1 1278.68  5140.7 1282.21  5176.1 1286.99  5207.7 1292.24
  5218.4 1293.15  5239.8 1297.78  5255.7 1300.06  5310.4 1316.59  5325.5 1317.52
#Mann=5,-1,0
  4660.6    0.12       0  4676.9    0.05       0  4854.1    0.12       0
  5004.4    0.07       0  5008.4    0.12       0
Bank Sta=5004.4,5008.4
Exp/Cntr=0.3,0.1

Type RM Length L Ch R = 1,28278,488,488,488
BEGIN DESCRIPTION:
REED CREEK 58.0
END DESCRIPTION:
XS GIS Cut Line= 3
      2829105.67     10272503.12      2828822.50     10272578.00
      2828505.72     10272453.13
#Sta/Elev= 30
  4707.1 1273.13  4724.6 1270.81  4748.5 1269.56  4758.8 1268.22  4764.9 1266.64
  4805.1 1263.16  4840.2 1253.58  4845.4 1253.85  4851.9 1252.22  4863.2 1252.44
  4885.6 1253.36  4903.6 1252.64  4966.1 1253.55  4986.4 1253.23  5016.1 1250.96
  5016.3 1247.96  5019.8 1247.96  5020.1 1250.96  5079.3 1252.26  5084.7 1256.11
  5103.7 1257.85  5109.1 1260.13  5125.6 1260.38  5133.5 1259.04  5138.9 1260.33
  5147.1 1260.88  5168.6 1264.23  5222.8 1267.25  5301.3 1274.44  5340.5 1281.14
#Mann=4,-1,0
  4707.1    0.12       0  4863.2    0.05       0  5016.1    0.05       0
  5020.1    0.05       0
Bank Sta=5016.1,5020.1
Exp/Cntr=0.3,0.1

Type RM Length L Ch R = 1,27790,498,498,498
BEGIN DESCRIPTION:
REED CREEK 57.0
END DESCRIPTION:
XS GIS Cut Line= 3
      2829305.65     10272203.11      2828996.00     10272161.00
      2828805.67     10272003.10
#Sta/Elev= 30
  4687.5 1287.55  4728.7 1281.59  4778.3 1272.14  4808.6 1265.11  4889.3 1255.10
  4939.8 1252.98  4970.6 1247.36  4990.2 1245.86  5011.4 1245.84  5011.7 1242.84
  5015.2 1242.84  5015.4 1245.84  5020.0 1246.83  5026.5 1246.35  5034.4 1248.46
  5040.9 1246.88  5055.2 1247.09  5083.9 1248.35  5104.7 1250.47  5112.5 1253.85
  5119.0 1252.73  5147.7 1257.93  5155.5 1260.65  5165.8 1261.47  5176.3 1263.04
  5182.8 1262.85  5197.1 1265.79  5240.1 1269.65  5244.0 1271.40  5247.3 1271.40
#Mann=5,-1,0
  4687.5    0.12       0  4970.6    0.05       0  5011.4    0.05       0
  5015.4    0.05       0  5165.8    0.12       0
Bank Sta=5011.4,5015.4
Exp/Cntr=0.3,0.1

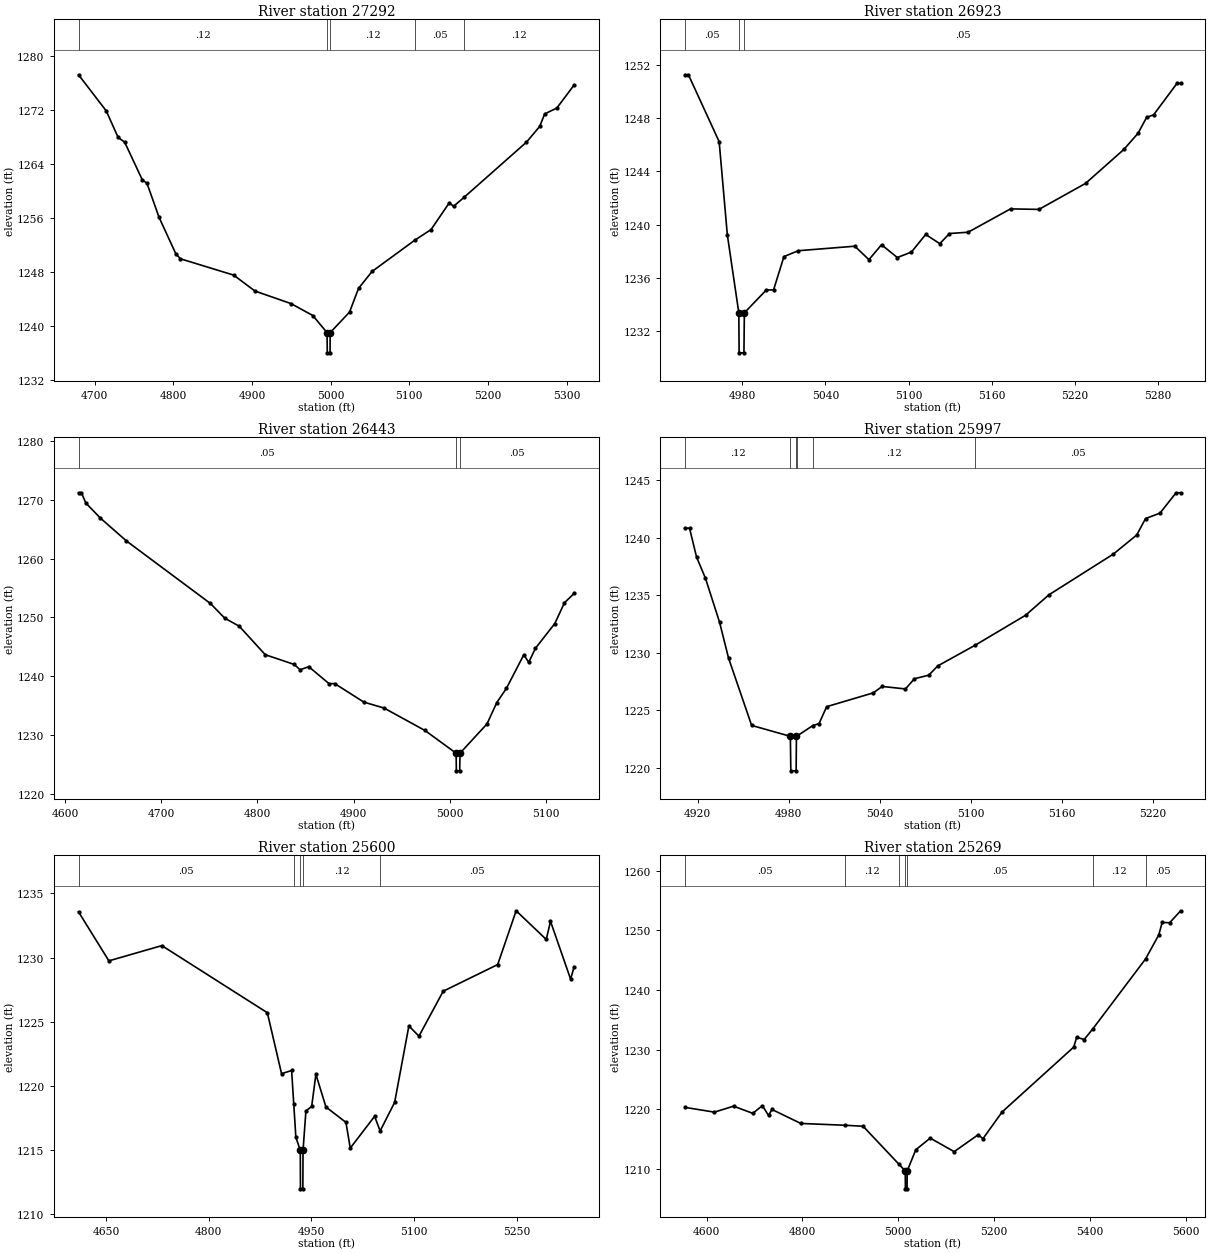
Type RM Length L Ch R = 1,27292,369,369,369
BEGIN DESCRIPTION:
REED CREEK 56.0
END DESCRIPTION:
XS GIS Cut Line= 3
      2829355.69     10272003.13      2829188.00     10271730.00
      2828905.70     10271603.12
#Sta/Elev= 30
  4679.5 1277.28  4714.7 1271.93  4729.8 1267.99  4738.2 1267.27  4760.7 1261.65
  4766.5 1261.18  4781.9 1256.11  4803.2 1250.70  4809.1 1249.96  4876.7 1247.54
  4903.8 1245.17  4949.4 1243.32  4977.3 1241.54  4995.4 1239.00  4995.7 1236.00
  4999.2 1236.00  4999.4 1239.00  5024.0 1242.05  5035.4 1245.56  5052.6 1248.08
  5106.9 1252.72  5127.6 1254.30  5150.8 1258.28  5156.2 1257.75  5169.8 1259.11
  5248.9 1267.28  5265.7 1269.61  5272.0 1271.46  5287.6 1272.36  5309.5 1275.77
#Mann=5,-1,0
  4679.5    0.12       0  4995.4    0.07       0  4999.4    0.12       0
  5106.9    0.05       0  5169.8    0.12       0
Bank Sta=4995.4,4999.4
Exp/Cntr=0.3,0.1

Type RM Length L Ch R = 1,26923,480,480,480
BEGIN DESCRIPTION:
REED CREEK 55.0
END DESCRIPTION:
XS GIS Cut Line= 3
      2829505.64     10271453.12      2829445.50     10271466.00
      2829155.65     10271403.10
#Sta/Elev= 30
  4938.5 1251.25  4941.0 1251.25  4963.2 1246.23  4969.1 1239.24  4977.4 1233.39
  4977.6 1230.39  4981.1 1230.39  4981.4 1233.39  4997.3 1235.11  5002.5 1235.11
  5010.0 1237.61  5020.3 1238.05  5061.2 1238.39  5071.4 1237.38  5080.5 1238.50
  5091.9 1237.54  5102.1 1237.95  5112.4 1239.27  5122.6 1238.58  5129.6 1239.34
  5143.1 1239.44  5173.7 1241.19  5194.2 1241.15  5227.9 1243.10  5255.6 1245.65
  5265.9 1246.87  5272.0 1248.05  5277.1 1248.25  5294.0 1250.61  5296.6 1250.61
#Mann=3,-1,0
  4938.5    0.05       0  4977.4    0.05       0  4981.4    0.05       0
Bank Sta=4977.4,4981.4
Exp/Cntr=0.3,0.1

Type RM Length L Ch R = 1,26443,446,446,446
BEGIN DESCRIPTION:
REED CREEK 54.0
END DESCRIPTION:
XS GIS Cut Line= 3
      2829655.71     10271253.13      2829334.00     10271040.00
      2829205.67     10271053.11
#Sta/Elev= 30
  4614.1 1271.23  4617.1 1271.23  4621.7 1269.49  4636.7 1266.94  4663.8 1263.04
  4751.0 1252.40  4766.1 1249.87  4781.1 1248.51  4808.1 1243.66  4838.3 1242.00
  4844.2 1241.10  4853.3 1241.62  4874.4 1238.73  4880.3 1238.74  4910.5 1235.59
  4931.5 1234.58  4974.0 1230.76  5006.4 1226.89  5006.6 1223.89  5010.1 1223.89
  5010.4 1226.89  5038.5 1231.89  5048.6 1235.51  5058.6 1237.93  5076.7 1243.65
  5081.8 1242.35  5088.8 1244.76  5108.9 1248.97  5118.9 1252.50  5129.0 1254.10
#Mann=3,-1,0
  4614.1    0.05       0  5006.4    0.05       0  5010.4    0.05       0
Bank Sta=5006.4,5010.4
Exp/Cntr=0.3,0.1

Type RM Length L Ch R = 1,25997,397,397,397
BEGIN DESCRIPTION:
REED CREEK 53.0
END DESCRIPTION:
XS GIS Cut Line= 3
      2829405.69     10270553.11      2829331.50     10270601.00
      2829205.67     10270803.13
#Sta/Elev= 30
  4911.7 1240.82  4914.7 1240.82  4919.3 1238.32  4925.2 1236.46  4934.5 1232.63
  4940.4 1229.52  4955.6 1223.67  4981.1 1222.72  4981.4 1219.72  4984.9 1219.72
  4985.1 1222.72  4985.4 1222.74  4995.8 1223.65  5000.0 1223.83  5005.0 1225.30
  5035.7 1226.50  5041.6 1227.06  5056.9 1226.84  5062.8 1227.73  5072.3 1228.04
  5078.1 1228.84  5103.0 1230.66  5136.0 1233.25  5151.3 1235.02  5193.8 1238.57
  5209.2 1240.23  5215.0 1241.66  5224.5 1242.13  5235.1 1243.90  5238.1 1243.90
#Mann=6,-1,0
  4911.7    0.12       0  4981.1    0.07       0  4985.1    0.12       0
  4985.4    0.05       0  4995.8    0.12       0  5103.0    0.05       0
Bank Sta=4981.1,4985.1
Exp/Cntr=0.3,0.1

Type RM Length L Ch R = 1,25600,331,331,331
BEGIN DESCRIPTION:
Mapping XS 051ed89f
END DESCRIPTION:
XS GIS Cut Line= 3
      2829347.20     10270370.75      2829106.88     10270355.73
      2828716.33     10270641.12
#Sta/Elev= 30
  4609.6 1233.57  4654.0 1229.74  4731.4 1230.93  4885.6 1225.69  4906.4 1220.93
  4921.1 1221.18  4924.2 1218.58  4927.3 1215.97  4933.8 1214.94  4934.0 1211.94
  4937.5 1211.94  4937.8 1214.94  4942.0 1218.03  4950.4 1218.37  4956.6 1220.88
  4971.3 1218.33  5000.5 1217.13  5006.8 1215.12  5042.4 1217.60  5050.5 1216.46
  5071.7 1218.69  5092.5 1224.66  5107.2 1223.86  5142.7 1227.37  5222.3 1229.45
  5249.3 1233.65  5293.3 1231.41  5299.5 1232.83  5328.9 1228.31  5334.1 1229.29
#Mann=5,-1,0
  4609.6    0.05       0  4924.2    0.12       0  4933.8    0.07       0
  4937.8    0.12       0  5050.5    0.05       0
Bank Sta=4933.8,4937.8
Exp/Cntr=0.3,0.1

Type RM Length L Ch R = 1,25269,678,678,678
BEGIN DESCRIPTION:
Mapping XS c379caa9
END DESCRIPTION:
XS GIS Cut Line= 3
      2829197.01     10270265.60      2828506.02     10270235.55
      2828205.61     10270070.33
#Sta/Elev= 30
  4555.0 1220.33  4616.4 1219.53  4656.4 1220.53  4696.5 1219.33  4716.5 1220.62
  4729.4 1218.98  4736.5 1219.98  4796.6 1217.64  4889.1 1217.33  4926.7 1217.17
  5001.5 1210.81  5014.8 1209.68  5015.0 1206.68  5018.5 1206.68  5018.8 1209.68
  5036.8 1213.23  5066.8 1215.18  5116.9 1212.91  5166.9 1215.74  5176.9 1215.08
  5217.0 1219.57  5366.4 1230.43  5372.6 1232.08  5388.1 1231.70  5406.1 1233.47
  5516.2 1245.19  5543.8 1249.21  5551.0 1251.32  5566.6 1251.26  5589.5 1253.27
#Mann=7,-1,0
  4555.0    0.05       0  4889.1    0.12       0  5001.5    0.05       0
  5014.8    0.07       0  5018.8    0.05       0  5406.1    0.12       0
  5516.2    0.05       0
Bank Sta=5014.8,5018.8
Exp/Cntr=0.3,0.1

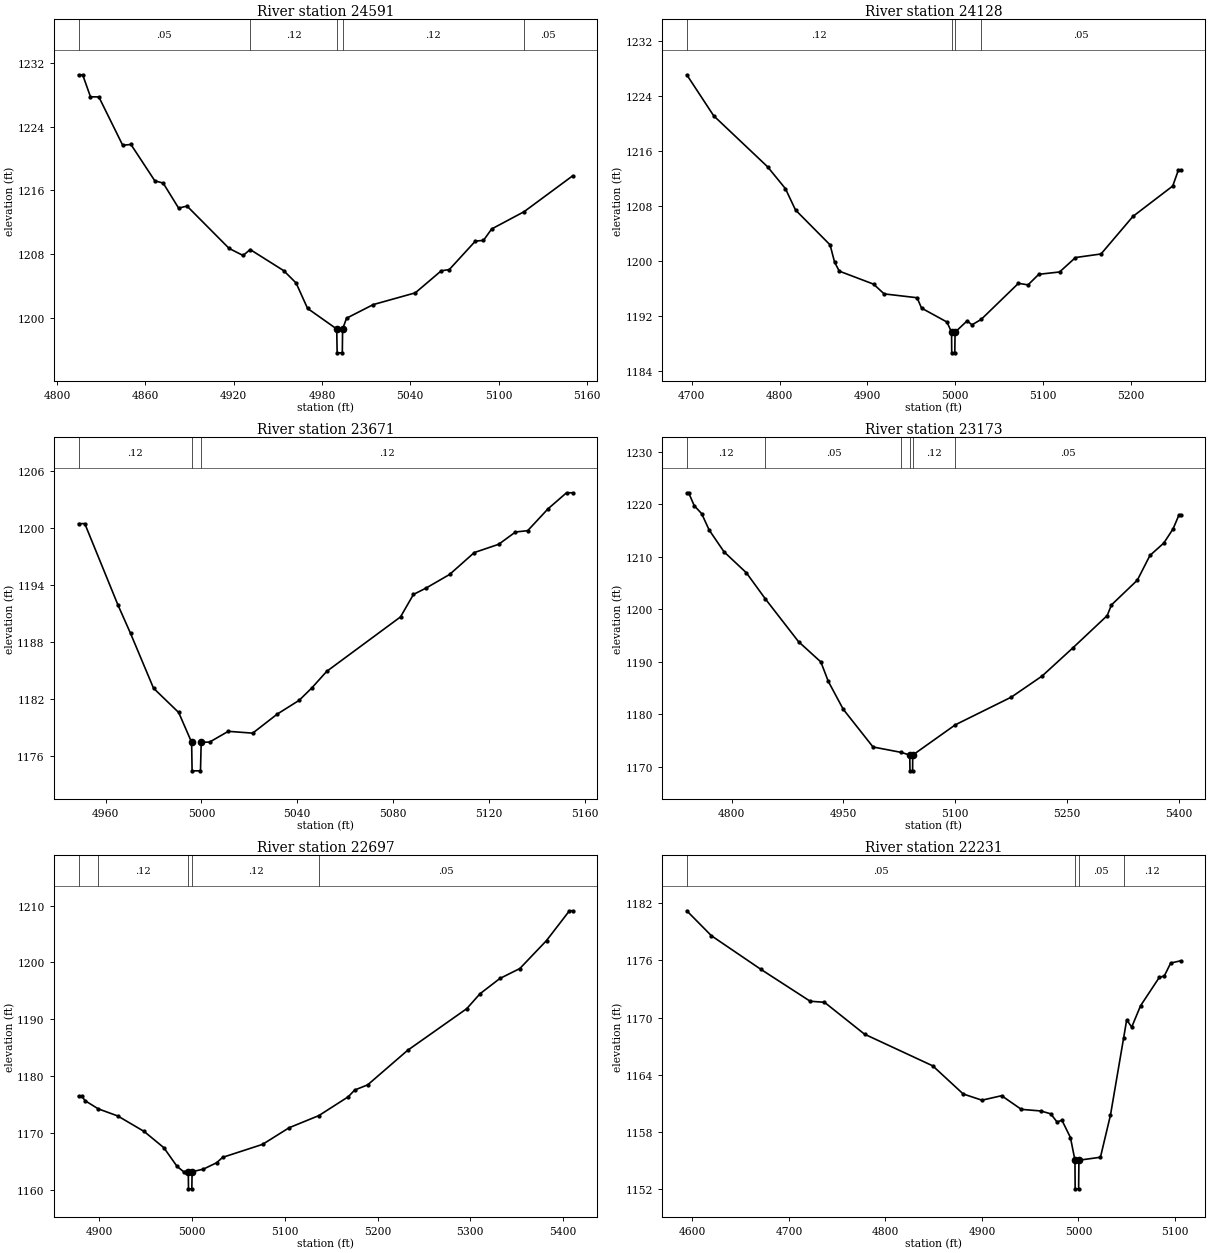
Type RM Length L Ch R = 1,24591,463,463,463
BEGIN DESCRIPTION:
REED CREEK 50.0
END DESCRIPTION:
XS GIS Cut Line= 3
      2829405.67     10270253.09      2829317.50     10270090.00
      2829255.68     10269953.11
#Sta/Elev= 30
  4814.6 1230.56  4817.4 1230.56  4822.7 1227.79  4828.4 1227.77  4844.6 1221.69
  4850.2 1221.79  4866.4 1217.22  4872.1 1216.93  4882.6 1213.78  4888.3 1214.04
  4916.9 1208.71  4926.4 1207.82  4931.2 1208.57  4954.0 1205.91  4962.4 1204.36
  4970.2 1201.16  4990.0 1198.57  4990.3 1195.57  4993.8 1195.57  4994.0 1198.57
  4996.7 1199.93  5014.8 1201.64  5043.4 1203.12  5061.0 1205.89  5066.5 1206.05
  5084.2 1209.63  5089.7 1209.72  5095.3 1211.16  5117.3 1213.33  5150.2 1217.83
#Mann=5,-1,0
  4814.6    0.05       0  4931.2    0.12       0  4990.0    0.07       0
  4994.0    0.12       0  5117.3    0.05       0
Bank Sta=4990,4994
Exp/Cntr=0.3,0.1

Type RM Length L Ch R = 1,24128,457,457,457
BEGIN DESCRIPTION:
REED CREEK 49.0
END DESCRIPTION:
XS GIS Cut Line= 3
      2829655.68     10270053.10      2829592.00     10269754.00
      2829355.64     10269653.09
#Sta/Elev= 30
  4694.2 1227.11  4724.9 1221.14  4786.2 1213.73  4806.6 1210.54  4818.1 1207.43
  4857.5 1202.35  4862.6 1199.84  4868.0 1198.53  4907.0 1196.64  4919.1 1195.22
  4956.6 1194.66  4961.7 1193.15  4990.7 1191.12  4995.9 1189.64  4996.1 1186.64
  4999.6 1186.64  4999.9 1189.64  5013.7 1191.30  5019.1 1190.71  5029.7 1191.51
  5072.1 1196.76  5083.0 1196.53  5095.3 1198.07  5119.0 1198.41  5137.1 1200.51
  5166.2 1201.03  5202.6 1206.50  5247.9 1210.92  5254.2 1213.19  5257.0 1213.19
#Mann=4,-1,0
  4694.2    0.12       0  4995.9    0.07       0  4999.9    0.12       0
  5029.7    0.05       0
Bank Sta=4995.9,4999.9
Exp/Cntr=0.3,0.1

Type RM Length L Ch R = 1,23671,498,498,498
BEGIN DESCRIPTION:
REED CREEK 48.0
END DESCRIPTION:
XS GIS Cut Line= 3
      2829905.68     10269953.11      2829920.50     10269904.00
      2829955.68     10269753.15
#Sta/Elev= 28
  4948.7 1200.43  4951.3 1200.43  4965.2 1191.85  4970.4 1188.90  4980.0 1183.14
  4990.5 1180.59  4995.9 1177.46  4996.1 1174.46  4999.6 1174.46  4999.9 1177.46
  5003.4 1177.48  5011.2 1178.61  5021.4 1178.42  5031.7 1180.43  5040.8 1181.87
  5046.0 1183.15  5052.3 1184.91  5083.1 1190.63  5088.5 1192.99  5093.7 1193.65
  5103.6 1195.09  5113.9 1197.39  5124.1 1198.26  5131.1 1199.55  5136.2 1199.69
  5144.7 1201.99  5152.4 1203.67  5154.9 1203.67
#Mann=3,-1,0
  4948.7    0.12       0  4995.9    0.07       0  4999.9    0.12       0
Bank Sta=4995.9,4999.9
Exp/Cntr=0.3,0.1

Type RM Length L Ch R = 1,23173,476,476,476
BEGIN DESCRIPTION:
REED CREEK 47.0
END DESCRIPTION:
XS GIS Cut Line= 3
      2830405.68     10270253.10      2830407.25     10269993.00
      2830305.68     10269603.11
#Sta/Elev= 30
  4739.9 1222.18  4742.4 1222.18  4749.9 1219.73  4759.9 1218.21  4769.9 1215.11
  4789.9 1210.95  4819.9 1206.96  4845.5 1201.97  4889.9 1193.86  4919.9 1189.99
  4929.9 1186.29  4949.9 1181.00  4989.9 1173.82  5028.1 1172.78  5039.2 1172.28
  5039.5 1169.28  5043.0 1169.28  5043.2 1172.28  5100.4 1178.04  5175.6 1183.31
  5216.9 1187.32  5258.2 1192.68  5304.2 1198.81  5309.9 1200.84  5344.7 1205.56
  5361.6 1210.26  5380.1 1212.60  5392.6 1215.30  5400.3 1217.88  5402.9 1217.88
#Mann=6,-1,0
  4739.9    0.12       0  4845.5    0.05       0  5028.1    0.12       0
  5039.2    0.05       0  5043.2    0.12       0  5100.4    0.05       0
Bank Sta=5039.2,5043.2
Exp/Cntr=0.3,0.1

Type RM Length L Ch R = 1,22697,466,466,466
BEGIN DESCRIPTION:
REED CREEK 46.0
END DESCRIPTION:
XS GIS Cut Line= 3
      2830905.67     10269853.10      2830820.25     10269766.00
      2830505.65     10269503.08
#Sta/Elev= 30
  4878.0 1176.52  4881.5 1176.52  4885.1 1175.72  4899.2 1174.30  4920.3 1173.04
  4948.6 1170.33  4969.9 1167.47  4984.1 1164.19  4991.1 1163.27  4996.2 1163.25
  4996.4 1160.25  5000.0 1160.25  5000.3 1163.25  5012.4 1163.71  5026.7 1164.83
  5033.2 1165.78  5076.2 1168.06  5104.8 1170.98  5136.8 1173.11  5168.5 1176.42
  5175.4 1177.60  5189.4 1178.51  5232.3 1184.56  5296.1 1191.89  5310.4 1194.51
  5331.8 1197.19  5353.3 1198.94  5382.0 1203.85  5406.7 1209.08  5410.0 1209.08
#Mann=5,-1,0
  4878.0    0.05       0  4899.2    0.12       0  4996.2    0.07       0
  5000.3    0.12       0  5136.8    0.05       0
Bank Sta=4996.2,5000.3
Exp/Cntr=0.3,0.1

Type RM Length L Ch R = 1,22231,463,463,463
BEGIN DESCRIPTION:
REED CREEK 45.0
END DESCRIPTION:
XS GIS Cut Line= 3
      2831155.68     10269953.12      2831234.75     10269555.00
      2831205.67     10269453.07
#Sta/Elev= 30
  4594.1 1181.19  4619.7 1178.57  4670.8 1175.06  4722.0 1171.71  4736.8 1171.60
  4778.3 1168.26  4849.0 1164.94  4880.6 1161.99  4900.0 1161.34  4920.4 1161.81
  4940.8 1160.38  4961.1 1160.21  4971.3 1159.91  4977.8 1159.06  4982.9 1159.24
  4991.7 1157.43  4996.4 1155.05  4996.6 1152.05  5000.2 1152.05  5000.5 1155.05
  5022.8 1155.36  5033.2 1159.78  5046.9 1167.90  5050.0 1169.76  5055.2 1169.00
  5064.4 1171.24  5083.8 1174.21  5089.0 1174.36  5095.6 1175.71  5106.0 1175.95
#Mann=4,-1,0
  4594.1    0.05       0  4996.4    0.05       0  5000.5    0.05       0
  5046.9    0.12       0
Bank Sta=4996.4,5000.5
Exp/Cntr=0.3,0.1

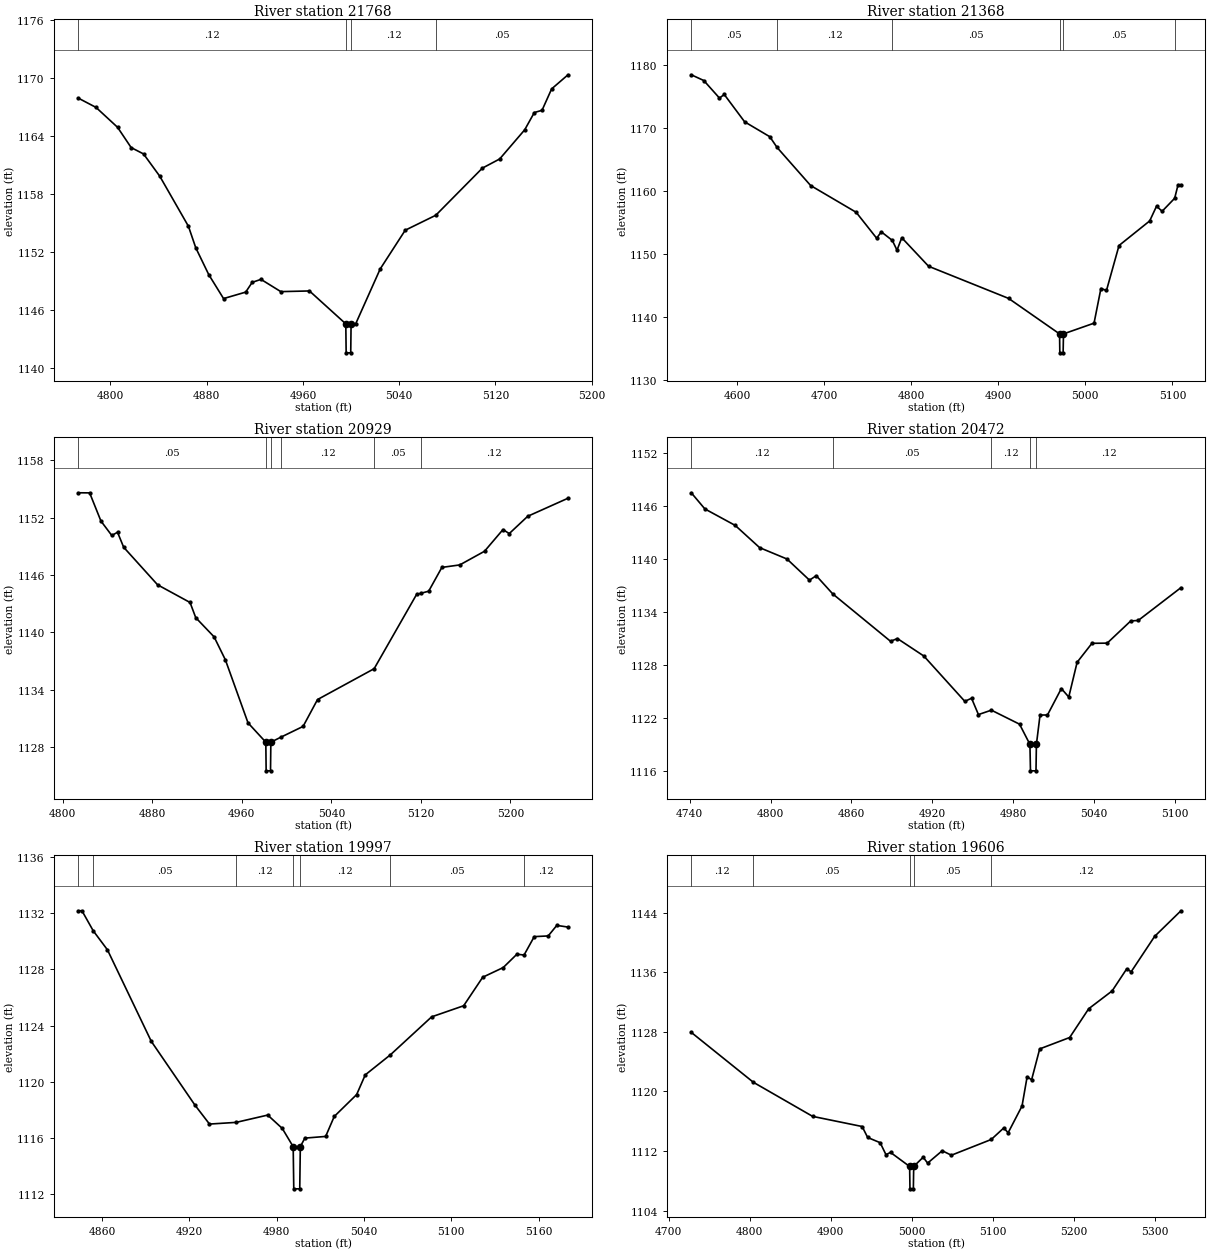
Type RM Length L Ch R = 1,21768,400,400,400
BEGIN DESCRIPTION:
REED CREEK 44.0
END DESCRIPTION:
XS GIS Cut Line= 3
      2831755.70     10269703.15      2831668.25     10269494.00
      2831555.71     10269353.14
#Sta/Elev= 30
  4773.3 1167.91  4788.0 1166.95  4805.9 1164.89  4817.2 1162.79  4827.5 1162.13
  4841.0 1159.82  4864.8 1154.64  4870.9 1152.41  4881.7 1149.63  4894.0 1147.15
  4912.4 1147.82  4917.8 1148.83  4925.1 1149.14  4941.6 1147.87  4965.4 1147.94
  4995.6 1144.53  4995.9 1141.53  4999.7 1141.53  5000.0 1144.53  5003.8 1144.53
  5024.2 1150.22  5045.0 1154.23  5070.4 1155.78  5109.1 1160.66  5123.5 1161.61
  5144.3 1164.63  5152.3 1166.42  5158.7 1166.65  5166.7 1168.87  5180.3 1170.33
#Mann=4,-1,0
  4773.3    0.12       0  4995.6    0.07       0  5000.0    0.12       0
  5070.4    0.05       0
Bank Sta=4995.6,5000
Exp/Cntr=0.3,0.1

Type RM Length L Ch R = 1,21368,439,439,439
BEGIN DESCRIPTION:
REED CREEK 43.0
END DESCRIPTION:
XS GIS Cut Line= 3
      2832205.67     10269753.08      2832025.25     10269338.00
      2831955.65     10269253.07
#Sta/Elev= 30
  4547.4 1178.41  4561.8 1177.50  4579.8 1174.72  4585.3 1175.29  4608.7 1170.96
  4637.6 1168.60  4645.9 1166.91  4684.5 1160.87  4736.8 1156.63  4760.3 1152.53
  4765.7 1153.53  4778.3 1152.18  4783.7 1150.63  4789.2 1152.60  4820.0 1148.08
  4911.9 1142.99  4970.4 1137.37  4970.7 1134.37  4974.5 1134.37  4974.9 1137.37
  5010.0 1139.07  5017.9 1144.56  5024.3 1144.25  5038.7 1151.37  5073.9 1155.26
  5081.8 1157.60  5088.2 1156.79  5102.6 1158.85  5106.5 1160.99  5109.8 1160.99
#Mann=6,-1,0
  4547.4    0.05       0  4645.9    0.12       0  4778.3    0.05       0
  4970.4    0.05       0  4974.9    0.05       0  5102.6    0.12       0
Bank Sta=4970.4,4974.9
Exp/Cntr=0.3,0.1

Type RM Length L Ch R = 1,20929,457,457,457
BEGIN DESCRIPTION:
REED CREEK 42.0
END DESCRIPTION:
XS GIS Cut Line= 3
      2832455.69     10269403.14      2832428.75     10269219.00
      2832205.66     10269103.10
#Sta/Elev= 30
  4813.9 1154.61  4824.0 1154.60  4834.1 1151.65  4843.8 1150.14  4848.9 1150.48
  4854.4 1148.91  4884.7 1144.98  4913.7 1143.13  4918.8 1141.54  4935.2 1139.53
  4945.3 1137.12  4965.5 1130.53  4981.4 1128.51  4981.7 1125.51  4985.6 1125.51
  4985.9 1128.51  4995.0 1129.04  5014.7 1130.16  5027.6 1132.97  5078.2 1136.20
  5116.1 1143.97  5119.9 1144.09  5126.9 1144.31  5138.7 1146.80  5154.7 1147.06
  5176.8 1148.49  5193.3 1150.76  5198.9 1150.34  5215.4 1152.15  5251.4 1154.04
#Mann=6,-1,0
  4813.9    0.05       0  4981.4    0.07       0  4985.9    0.05       0
  4995.0    0.12       0  5078.2    0.05       0  5119.9    0.12       0
Bank Sta=4981.4,4985.9
Exp/Cntr=0.3,0.1

Type RM Length L Ch R = 1,20472,475,475,475
BEGIN DESCRIPTION:
REED CREEK 41.0
END DESCRIPTION:
XS GIS Cut Line= 3
      2832805.69     10269303.11      2832849.25     10269048.00
      2832805.69     10268953.12
#Sta/Elev= 30
  4741.2 1147.54  4751.3 1145.71  4773.8 1143.84  4791.9 1141.32  4812.2 1140.03
  4828.9 1137.63  4833.9 1138.14  4846.1 1136.08  4889.0 1130.70  4894.1 1131.01
  4913.7 1129.03  4944.1 1123.89  4949.1 1124.24  4954.2 1122.39  4963.8 1122.89
  4984.7 1121.30  4992.4 1119.01  4992.8 1116.01  4996.9 1116.01  4997.2 1119.01
  4999.9 1122.34  5005.4 1122.34  5015.7 1125.34  5021.2 1124.38  5027.4 1128.32
  5038.4 1130.47  5049.7 1130.49  5067.2 1133.01  5072.7 1133.06  5104.4 1136.78
#Mann=5,-1,0
  4741.2    0.12       0  4846.1    0.05       0  4963.8    0.12       0
  4992.4    0.07       0  4997.2    0.12       0
Bank Sta=4992.4,4997.2
Exp/Cntr=0.3,0.1

Type RM Length L Ch R = 1,19997,391,391,391
BEGIN DESCRIPTION:
REED CREEK 40.0
END DESCRIPTION:
XS GIS Cut Line= 3
      2833305.68     10269103.15      2833309.50     10268947.00
      2833155.69     10268853.11
#Sta/Elev= 30
  4843.8 1132.17  4846.3 1132.17  4854.0 1130.75  4863.8 1129.39  4893.9 1122.88
  4923.9 1118.34  4933.9 1116.99  4952.2 1117.11  4973.9 1117.63  4983.9 1116.68
  4991.4 1115.38  4991.8 1112.38  4995.9 1112.38  4996.3 1115.38  4999.4 1115.99
  5013.7 1116.11  5019.6 1117.53  5035.0 1119.09  5040.9 1120.49  5058.2 1121.92
  5086.5 1124.62  5108.5 1125.41  5121.6 1127.44  5135.7 1128.13  5145.1 1129.08
  5150.0 1129.02  5157.0 1130.33  5166.6 1130.38  5172.5 1131.13  5180.2 1131.01
#Mann=7,-1,0
  4843.8    0.12       0  4854.0    0.05       0  4952.2    0.12       0
  4991.4    0.07       0  4996.3    0.12       0  5058.2    0.05       0
  5150.0    0.12       0
Bank Sta=4991.4,4996.3
Exp/Cntr=0.3,0.1

Type RM Length L Ch R = 1,19606,490,490,490
BEGIN DESCRIPTION:
REED CREEK 39.0
END DESCRIPTION:
XS GIS Cut Line= 3
      2833555.67     10269053.14      2833673.75     10268808.00
      2833805.68     10268503.12
#Sta/Elev= 30
  4727.9 1127.93  4804.6 1121.23  4877.7 1116.66  4938.8 1115.30  4945.6 1113.83
  4961.0 1113.13  4968.2 1111.52  4973.8 1111.83  4997.4 1109.94  4997.8 1106.94
  5002.0 1106.94  5002.4 1109.94  5014.1 1111.18  5019.6 1110.39  5037.6 1112.05
  5048.9 1111.45  5098.1 1113.56  5113.5 1115.10  5119.0 1114.47  5136.1 1118.05
  5142.4 1121.98  5147.9 1121.56  5157.9 1125.71  5194.9 1127.24  5218.4 1131.10
  5247.3 1133.49  5265.3 1136.45  5270.8 1136.06  5299.7 1140.80  5332.2 1144.24
#Mann=5,-1,0
  4727.9    0.12       0  4804.6    0.05       0  4997.4    0.05       0
  5002.4    0.05       0  5098.1    0.12       0
Bank Sta=4997.4,5002.4
Exp/Cntr=0.3,0.1