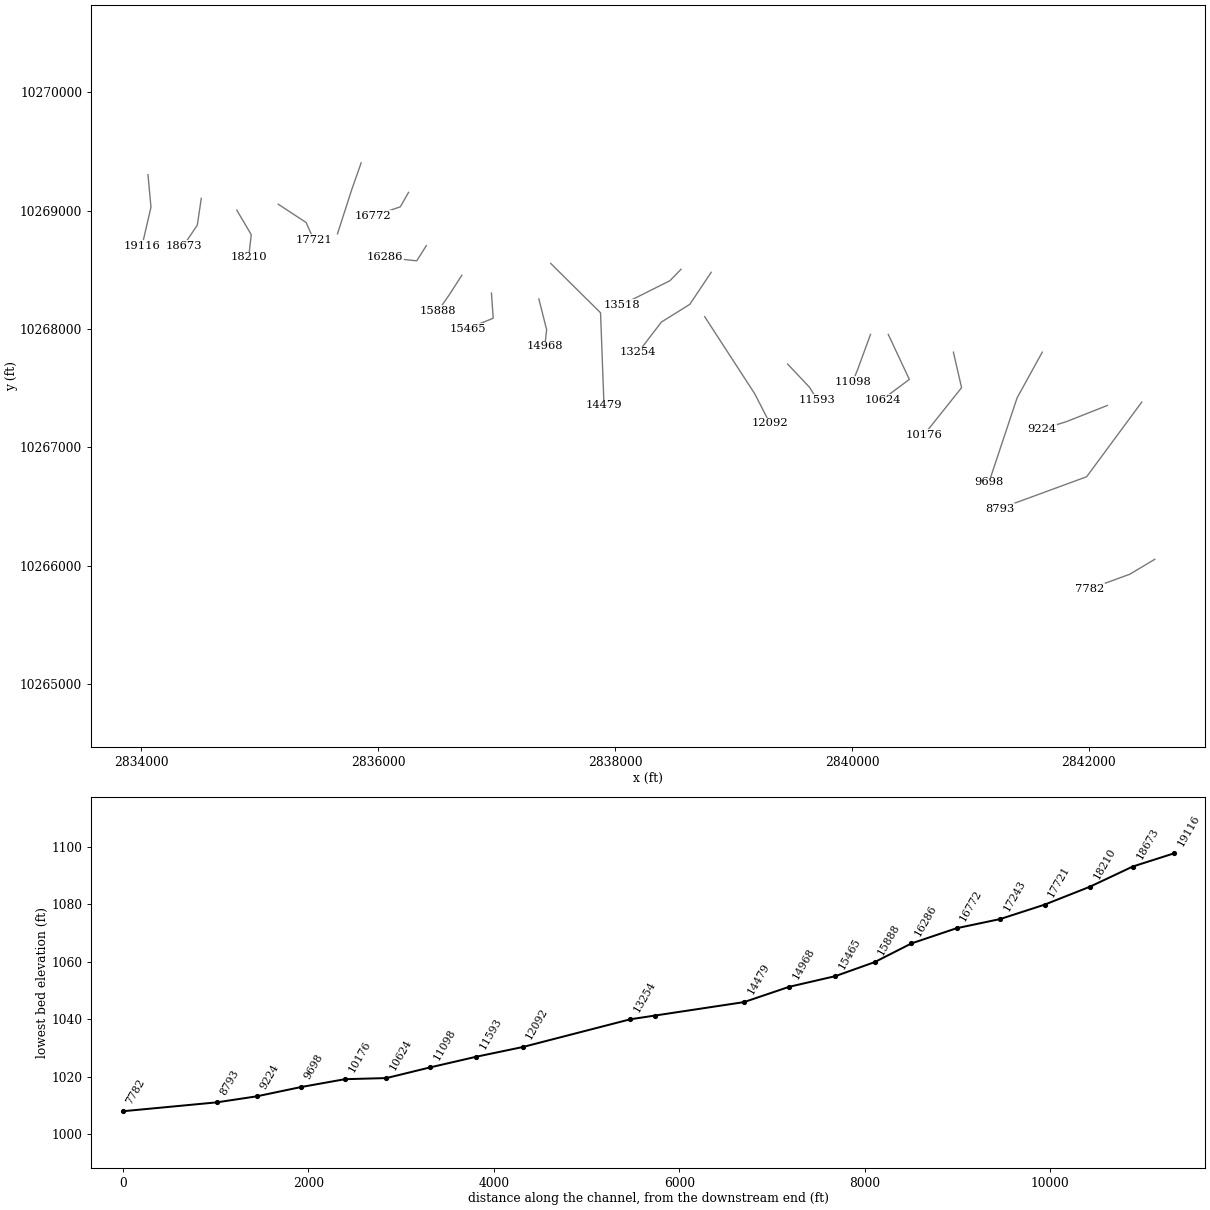
HEC-RAS study REED CREEK.prj: REED CREEK Base Level Engineering

--- REED CREEK.g01 (geometry) --- (continued)

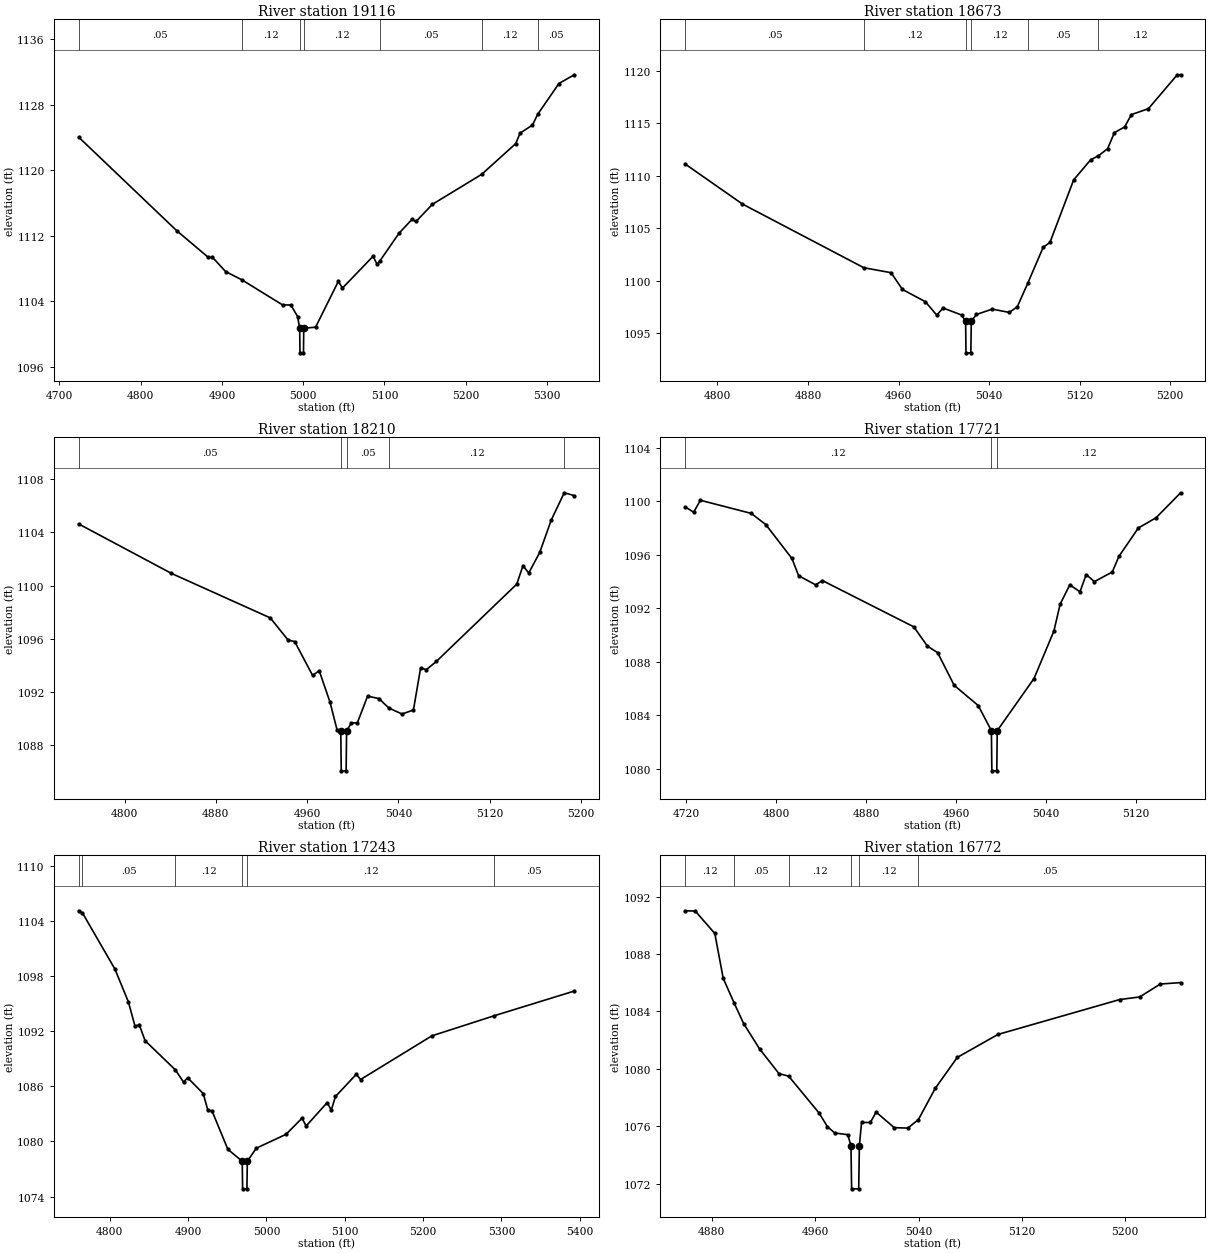
Type RM Length L Ch R = 1,19116,443,443,443
BEGIN DESCRIPTION:
REED CREEK 38.0
END DESCRIPTION:
XS GIS Cut Line= 3
      2834055.68     10269303.14      2834081.00     10269028.00
      2834005.69     10268703.12
#Sta/Elev= 30
  4723.7 1124.06  4844.2 1112.64  4883.4 1109.35  4888.4 1109.37  4904.5 1107.63
  4924.8 1106.60  4974.8 1103.54  4984.8 1103.55  4993.2 1102.12  4995.7 1100.69
  4996.1 1097.69  5000.4 1097.69  5000.7 1100.69  5015.3 1100.83  5043.3 1106.43
  5048.4 1105.61  5086.0 1109.49  5091.1 1108.50  5094.1 1108.88  5117.9 1112.30
  5133.8 1113.99  5138.9 1113.75  5159.0 1115.84  5219.7 1119.51  5261.6 1123.27
  5266.9 1124.54  5282.2 1125.54  5288.7 1126.86  5314.7 1130.61  5333.5 1131.68
#Mann=7,-1,0
  4723.7    0.05       0  4924.8    0.12       0  4995.7    0.07       0
  5000.7    0.12       0  5094.1    0.05       0  5219.7    0.12       0
  5288.7    0.05       0
Bank Sta=4995.7,5000.7
Exp/Cntr=0.3,0.1

Type RM Length L Ch R = 1,18673,463,463,463
BEGIN DESCRIPTION:
REED CREEK 37.0
END DESCRIPTION:
XS GIS Cut Line= 3
      2834505.69     10269103.14      2834472.25     10268877.00
      2834355.71     10268703.15
#Sta/Elev= 30
  4771.4 1111.11  4822.0 1107.30  4929.4 1101.23  4953.4 1100.76  4963.5 1099.16
  4983.7 1098.00  4993.8 1096.72  4999.4 1097.40  5015.7 1096.73  5019.3 1096.13
  5019.6 1093.13  5023.9 1093.13  5024.3 1096.13  5028.8 1096.78  5042.8 1097.29
  5057.8 1096.98  5064.9 1097.50  5074.3 1099.78  5087.8 1103.17  5093.8 1103.64
  5114.8 1109.60  5129.8 1111.51  5136.7 1111.89  5144.8 1112.57  5150.8 1114.10
  5159.8 1114.63  5165.8 1115.81  5180.8 1116.37  5206.3 1119.60  5209.3 1119.60
#Mann=6,-1,0
  4771.4    0.05       0  4929.4    0.12       0  5019.3    0.07       0
  5024.3    0.12       0  5074.3    0.05       0  5136.7    0.12       0
Bank Sta=5019.3,5024.3
Exp/Cntr=0.3,0.1

Type RM Length L Ch R = 1,18210,489,489,489
BEGIN DESCRIPTION:
REED CREEK 36.0
END DESCRIPTION:
XS GIS Cut Line= 3
      2834805.67     10269003.13      2834927.50     10268796.00
      2834905.69     10268603.13
#Sta/Elev= 30
  4759.7 1104.64  4840.9 1100.93  4927.7 1097.58  4943.3 1095.92  4949.1 1095.80
  4964.8 1093.26  4970.6 1093.61  4980.1 1091.24  4986.3 1089.15  4989.5 1089.09
  4989.9 1086.09  4994.2 1086.09  4994.6 1089.09  4998.8 1089.69  5004.0 1089.69
  5013.0 1091.70  5023.0 1091.52  5031.6 1090.81  5043.2 1090.36  5053.2 1090.66
  5059.5 1093.83  5064.5 1093.69  5073.4 1094.32  5143.8 1100.12  5149.2 1101.50
  5154.3 1100.95  5163.9 1102.50  5174.0 1104.93  5185.4 1106.98  5194.1 1106.77
#Mann=5,-1,0
  4759.7    0.05       0  4989.5    0.05       0  4994.6    0.05       0
  5031.6    0.12       0  5185.4    0.05       0
Bank Sta=4989.5,4994.6
Exp/Cntr=0.3,0.1

Type RM Length L Ch R = 1,17721,478,478,478
BEGIN DESCRIPTION:
REED CREEK 35.0
END DESCRIPTION:
XS GIS Cut Line= 3
      2835155.66     10269053.13      2835390.50     10268899.00
      2835455.69     10268753.10
#Sta/Elev= 30
  4719.1 1099.58  4726.7 1099.18  4732.7 1100.07  4777.9 1099.09  4790.9 1098.25
  4814.1 1095.72  4820.1 1094.43  4835.2 1093.75  4841.2 1094.07  4922.5 1090.61
  4934.6 1089.17  4943.7 1088.68  4958.4 1086.24  4979.8 1084.73  4991.5 1082.85
  4991.9 1079.85  4996.3 1079.85  4996.7 1082.85  5029.4 1086.75  5047.1 1090.30
  5052.6 1092.30  5061.2 1093.75  5070.3 1093.23  5075.8 1094.52  5083.1 1093.99
  5099.0 1094.71  5105.0 1095.89  5122.2 1098.00  5137.9 1098.76  5159.8 1100.63
#Mann=3,-1,0
  4719.1    0.12       0  4991.5    0.07       0  4996.7    0.12       0
Bank Sta=4991.5,4996.7
Exp/Cntr=0.3,0.1

Type RM Length L Ch R = 1,17243,471,471,471
BEGIN DESCRIPTION:
REED CREEK 34.0
END DESCRIPTION:
XS GIS Cut Line= 3
      2835855.67     10269403.07      2835776.00     10269177.00
      2835655.68     10268803.08
#Sta/Elev= 30
  4760.3 1105.08  4765.1 1104.86  4806.7 1098.73  4823.9 1095.15  4832.3 1092.52
  4837.6 1092.71  4845.1 1090.96  4883.7 1087.79  4894.2 1086.46  4899.5 1086.92
  4919.3 1085.21  4925.2 1083.41  4930.5 1083.33  4950.8 1079.14  4969.1 1077.85
  4969.6 1074.85  4975.1 1074.85  4975.6 1077.85  4987.1 1079.27  5025.1 1080.78
  5045.4 1082.53  5050.7 1081.68  5077.5 1084.22  5082.8 1083.41  5088.1 1084.89
  5114.8 1087.31  5120.1 1086.73  5211.1 1091.48  5290.8 1093.67  5392.8 1096.35
#Mann=6,-1,0
  4760.3    0.12       0  4765.1    0.05       0  4883.7    0.12       0
  4969.1    0.07       0  4975.6    0.12       0  5290.8    0.05       0
Bank Sta=4969.1,4975.6
Exp/Cntr=0.3,0.1

Type RM Length L Ch R = 1,16772,486,486,486
BEGIN DESCRIPTION:
REED CREEK 33.0
END DESCRIPTION:
XS GIS Cut Line= 3
      2836255.67     10269153.09      2836185.75     10269031.00
      2835955.68     10268953.11
#Sta/Elev= 30
  4859.3 1091.01  4867.2 1090.99  4882.3 1089.43  4888.8 1086.31  4897.1 1084.62
  4904.6 1083.16  4916.9 1081.40  4931.9 1079.68  4939.5 1079.49  4963.0 1076.93
  4969.4 1075.99  4975.1 1075.54  4985.2 1075.42  4987.7 1074.65  4988.2 1071.65
  4993.7 1071.65  4994.2 1074.65  4995.9 1076.27  5002.7 1076.27  5007.2 1076.99
  5021.2 1075.91  5031.7 1075.88  5039.9 1076.47  5052.9 1078.64  5070.0 1080.80
  5101.5 1082.40  5195.8 1084.83  5211.2 1085.01  5227.2 1085.91  5242.9 1086.01
#Mann=6,-1,0
  4859.3    0.12       0  4897.1    0.05       0  4939.5    0.12       0
  4987.7    0.07       0  4994.2    0.12       0  5039.9    0.05       0
Bank Sta=4987.7,4994.2
Exp/Cntr=0.3,0.1

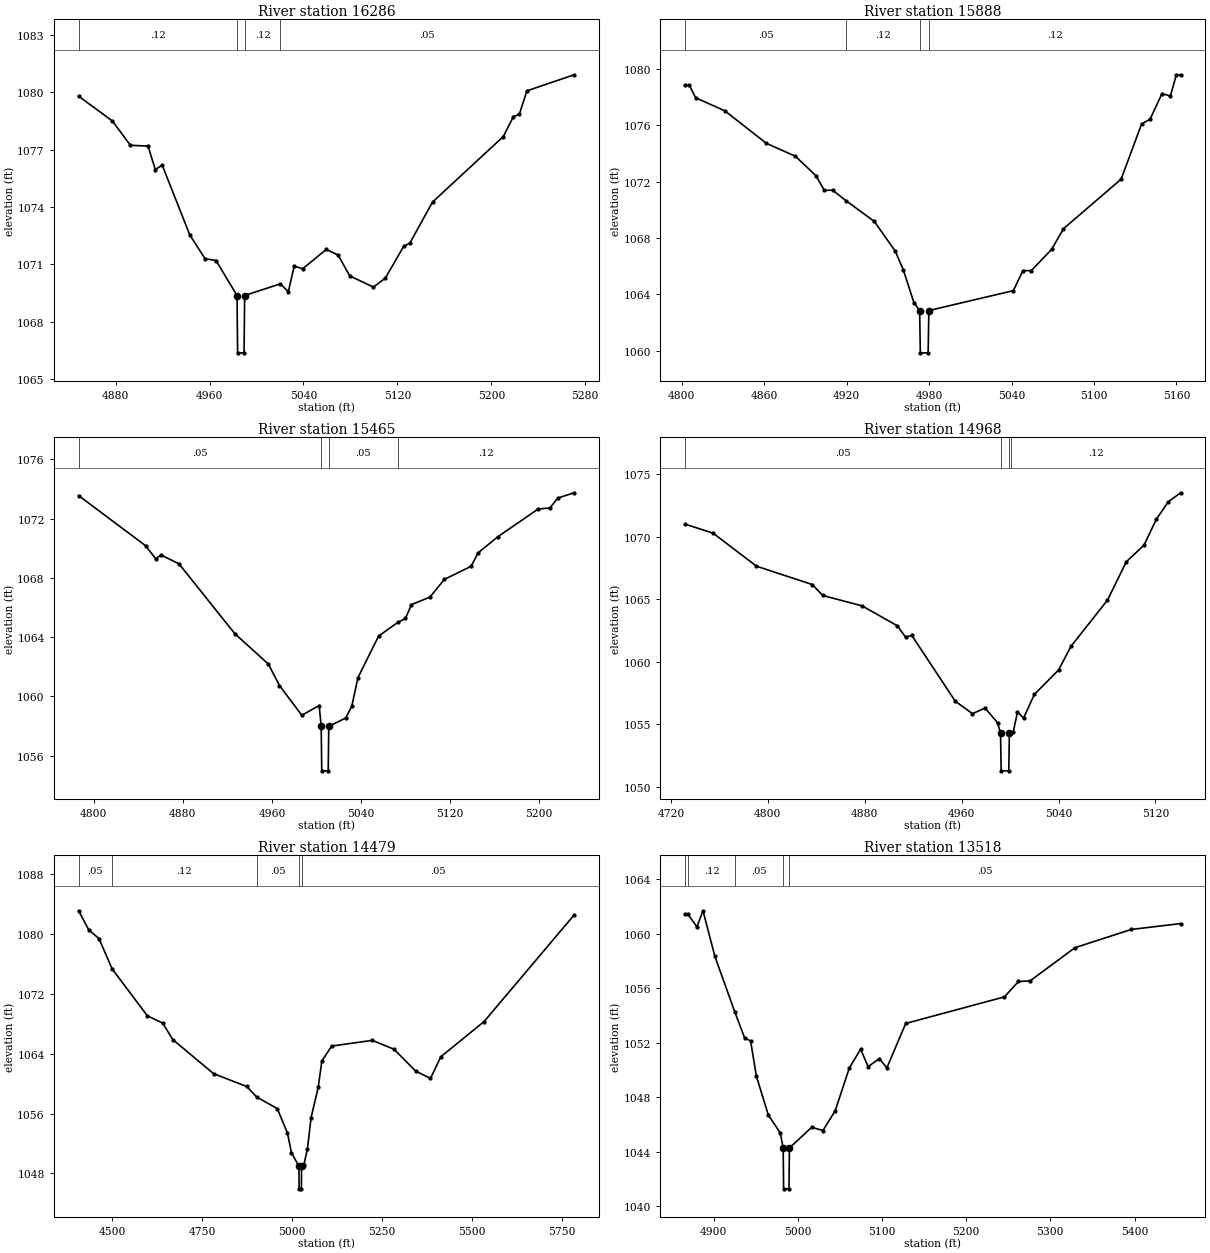
Type RM Length L Ch R = 1,16286,398,398,398
BEGIN DESCRIPTION:
REED CREEK 32.0
END DESCRIPTION:
XS GIS Cut Line= 3
      2836405.67     10268703.08      2836324.75     10268575.00
      2836055.71     10268603.11
#Sta/Elev= 30
  4848.5 1079.80  4877.3 1078.50  4892.6 1077.23  4907.6 1077.19  4913.8 1075.96
  4919.7 1076.19  4943.1 1072.55  4956.1 1071.30  4965.5 1071.20  4983.4 1069.37
  4983.9 1066.37  4989.4 1066.37  4989.9 1069.37  5020.3 1069.98  5027.1 1069.57
  5032.1 1070.91  5039.3 1070.77  5059.4 1071.78  5069.4 1071.49  5079.5 1070.39
  5099.6 1069.81  5109.7 1070.28  5125.5 1071.96  5130.5 1072.10  5149.9 1074.26
  5210.2 1077.69  5218.8 1078.73  5223.8 1078.85  5230.3 1080.08  5270.5 1080.92
#Mann=4,-1,0
  4848.5    0.12       0  4983.4    0.07       0  4989.9    0.12       0
  5020.3    0.05       0
Bank Sta=4983.4,4989.9
Exp/Cntr=0.3,0.1

Type RM Length L Ch R = 1,15888,423,423,423
BEGIN DESCRIPTION:
REED CREEK 31.0
END DESCRIPTION:
XS GIS Cut Line= 3
      2836705.71     10268453.15      2836598.75     10268287.00
      2836505.66     10268153.08
#Sta/Elev= 30
  4802.4 1078.84  4805.4 1078.84  4810.0 1077.94  4831.2 1077.02  4861.5 1074.71
  4882.7 1073.79  4897.6 1072.41  4903.8 1071.37  4909.7 1071.39  4919.4 1070.65
  4940.1 1069.17  4955.3 1067.07  4961.2 1065.74  4968.9 1063.42  4973.1 1062.85
  4973.6 1059.85  4979.3 1059.85  4979.8 1062.85  5041.3 1064.26  5048.3 1065.68
  5054.4 1065.68  5069.2 1067.19  5077.8 1068.65  5119.8 1072.17  5134.7 1076.09
  5140.8 1076.41  5149.5 1078.23  5155.6 1078.07  5160.0 1079.57  5163.1 1079.57
#Mann=4,-1,0
  4802.4    0.05       0  4919.4    0.12       0  4973.1    0.07       0
  4979.8    0.12       0
Bank Sta=4973.1,4979.8
Exp/Cntr=0.3,0.1

Type RM Length L Ch R = 1,15465,497,497,497
BEGIN DESCRIPTION:
REED CREEK 30.0
END DESCRIPTION:
XS GIS Cut Line= 3
      2836955.68     10268303.10      2836970.25     10268090.00
      2836755.68     10268003.11
#Sta/Elev= 30
  4786.4 1073.56  4846.5 1070.18  4855.6 1069.30  4860.6 1069.55  4876.6 1068.95
  4926.7 1064.24  4956.8 1062.19  4966.8 1060.74  4986.9 1058.73  5002.5 1059.39
  5004.3 1057.98  5004.8 1054.98  5010.6 1054.98  5011.1 1057.98  5026.4 1058.55
  5031.8 1059.35  5037.3 1061.27  5055.9 1064.08  5073.2 1065.00  5080.0 1065.27
  5085.4 1066.20  5102.0 1066.71  5114.9 1067.90  5139.0 1068.79  5145.2 1069.69
  5163.1 1070.79  5199.1 1072.65  5209.9 1072.73  5216.7 1073.39  5231.5 1073.75
#Mann=4,-1,0
  4786.4    0.05       0  5004.3    0.05       0  5011.1    0.05       0
  5073.2    0.12       0
Bank Sta=5004.3,5011.1
Exp/Cntr=0.3,0.1

Type RM Length L Ch R = 1,14968,489,489,489
BEGIN DESCRIPTION:
REED CREEK 29.0
END DESCRIPTION:
XS GIS Cut Line= 3
      2837355.69     10268253.10      2837421.50     10267993.00
      2837405.68     10267853.09
#Sta/Elev= 30
  4731.7 1071.00  4754.8 1070.28  4790.6 1067.64  4836.8 1066.17  4845.2 1065.30
  4877.8 1064.47  4907.0 1062.87  4913.7 1061.96  4918.8 1062.11  4954.7 1056.85
  4968.9 1055.85  4979.3 1056.30  4989.6 1055.13  4992.1 1054.28  4992.6 1051.28
  4998.9 1051.28  4999.4 1054.28  5000.8 1054.32  5002.5 1054.36  5006.1 1055.99
  5011.1 1055.49  5020.0 1057.39  5040.1 1059.35  5050.2 1061.23  5080.4 1064.93
  5095.9 1067.99  5110.6 1069.33  5120.7 1071.39  5130.7 1072.80  5140.8 1073.51
#Mann=4,-1,0
  4731.7    0.05       0  4992.1    0.05       0  4999.4    0.05       0
  5000.8    0.12       0
Bank Sta=4992.1,4999.4
Exp/Cntr=0.3,0.1

Type RM Length L Ch R = 1,14479,961,961,961
BEGIN DESCRIPTION:
REED CREEK 28.0
END DESCRIPTION:
XS GIS Cut Line= 3
      2837455.69     10268553.10      2837876.50     10268136.00
      2837905.68     10267353.14
#Sta/Elev= 30
  4407.5 1083.08  4435.7 1080.52  4464.0 1079.37  4500.5 1075.32  4598.4 1069.05
  4640.8 1068.08  4669.1 1065.87  4782.3 1061.32  4874.2 1059.61  4901.8 1058.21
  4959.0 1056.66  4987.3 1053.40  4998.5 1050.78  5019.3 1048.94  5019.8 1045.94
  5026.1 1045.94  5026.6 1048.94  5032.9 1049.10  5042.9 1051.31  5052.9 1055.43
  5072.9 1059.52  5082.9 1063.02  5110.1 1065.01  5223.0 1065.77  5283.1 1064.59
  5343.1 1061.68  5384.5 1060.69  5413.2 1063.58  5533.3 1068.28  5783.4 1082.52
#Mann=5,-1,0
  4407.5    0.05       0  4500.5    0.12       0  4901.8    0.05       0
  5019.3    0.05       0  5026.6    0.05       0
Bank Sta=5019.3,5026.6
Exp/Cntr=0.3,0.1

Type RM Length L Ch R = 1,13518,264,264,264
BEGIN DESCRIPTION:
REED CREEK 27.0
END DESCRIPTION:
XS GIS Cut Line= 3
      2838555.65     10268503.08      2838462.25     10268407.00
      2838055.71     10268203.12
#Sta/Elev= 30
  4866.0 1061.40  4869.4 1061.40  4880.0 1060.49  4887.2 1061.67  4901.3 1058.33
  4925.1 1054.23  4936.6 1052.35  4943.8 1052.11  4950.7 1049.52  4964.9 1046.67
  4979.0 1045.37  4982.5 1044.26  4983.0 1041.26  4989.4 1041.26  4989.9 1044.26
  5016.4 1045.78  5029.7 1045.54  5044.3 1046.99  5061.1 1050.13  5074.5 1051.51
  5083.4 1050.23  5096.8 1050.82  5105.7 1050.14  5128.1 1053.40  5245.4 1055.35
  5262.1 1056.48  5275.8 1056.52  5329.2 1058.96  5396.2 1060.30  5454.8 1060.73
#Mann=5,-1,0
  4866.0    0.05       0  4869.4    0.12       0  4925.1    0.05       0
  4982.5    0.05       0  4989.9    0.05       0
Bank Sta=4982.5,4989.9
Exp/Cntr=0.3,0.1

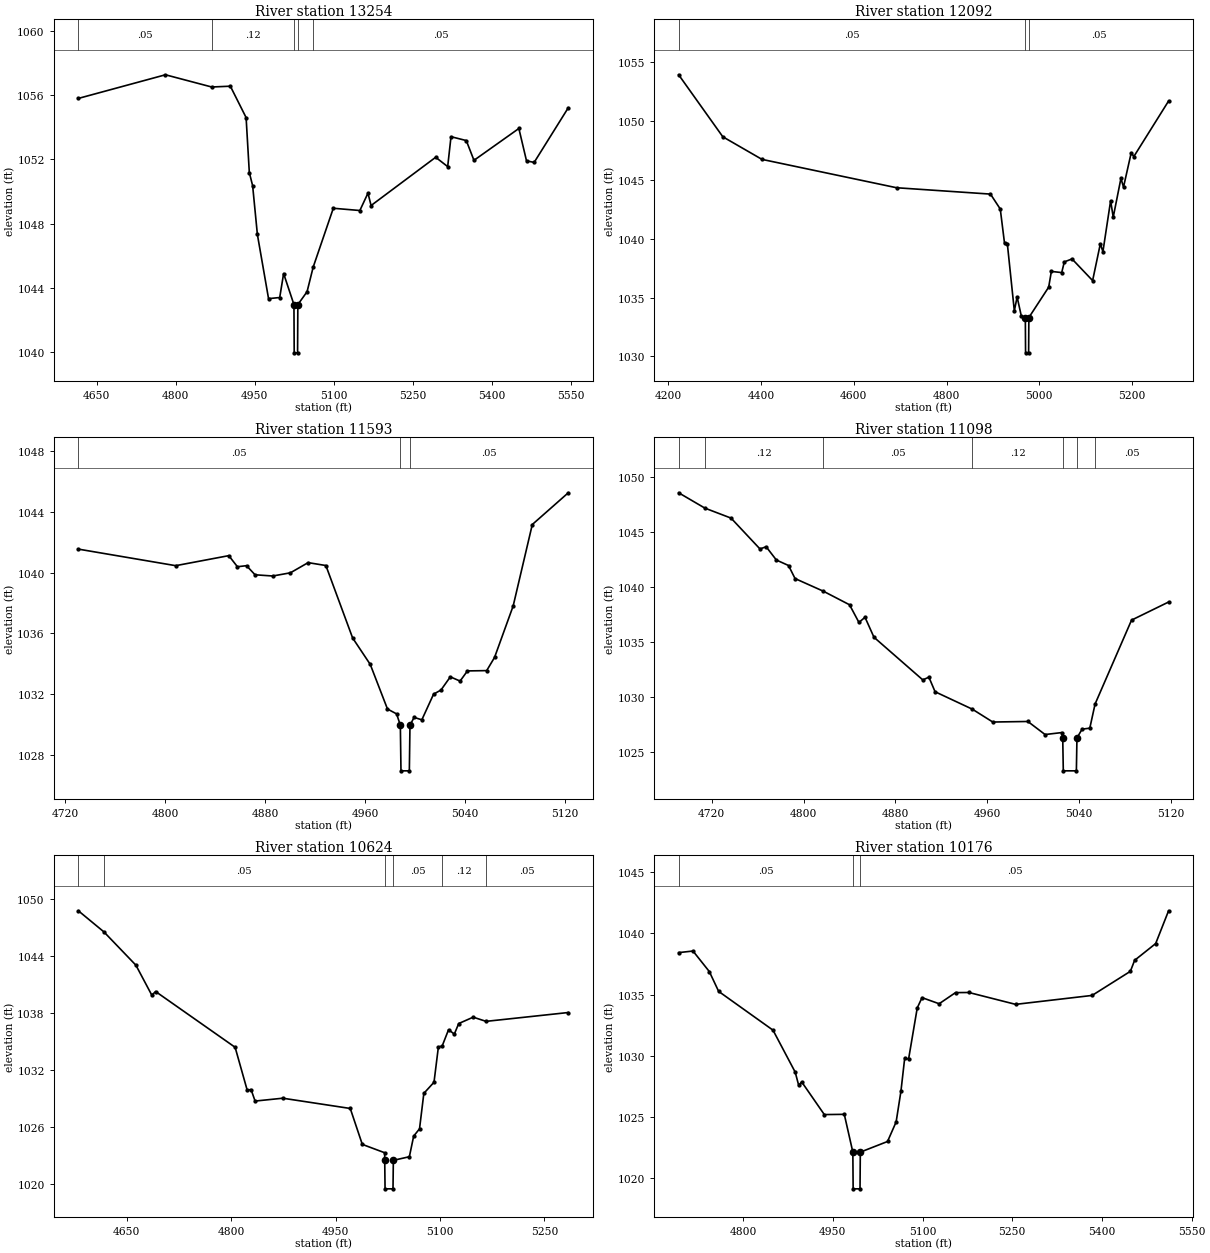
Type RM Length L Ch R = 1,13254,1162,1162,1162
BEGIN DESCRIPTION:
Mapping XS 5968f8f4
END DESCRIPTION:
XS GIS Cut Line= 4
      2838810.75     10268478.06      2838630.48     10268207.66
      2838390.14     10268057.44      2838194.85     10267802.06
#Sta/Elev= 30
  4615.5 1055.79  4780.8 1057.26  4868.6 1056.50  4904.0 1056.55  4933.9 1054.60
  4940.0 1051.18  4946.3 1050.36  4955.3 1047.33  4976.5 1043.34  4997.7 1043.41
  5005.1 1044.90  5024.7 1042.97  5025.2 1039.97  5031.6 1039.97  5032.1 1042.97
  5049.6 1043.77  5061.2 1045.30  5099.4 1048.96  5149.8 1048.82  5165.2 1049.90
  5171.1 1049.13  5293.7 1052.13  5316.5 1051.55  5322.8 1053.41  5351.8 1053.17
  5366.4 1051.94  5451.6 1053.92  5466.1 1051.91  5480.6 1051.81  5545.4 1055.21
#Mann=5,-1,0
  4615.5    0.05       0  4868.6    0.12       0  5024.7    0.07       0
  5032.1    0.12       0  5061.2    0.05       0
Bank Sta=5024.7,5032.1
Exp/Cntr=0.3,0.1

Type RM Length L Ch R = 1,12092,499,499,499
BEGIN DESCRIPTION:
REED CREEK 25.0
END DESCRIPTION:
XS GIS Cut Line= 3
      2838755.70     10268103.09      2839178.75     10267451.00
      2839305.69     10267203.11
#Sta/Elev= 30
  4222.7 1053.93  4317.9 1048.66  4402.3 1046.74  4692.4 1044.33  4894.7 1043.79
  4915.8 1042.52  4925.0 1039.60  4931.0 1039.58  4946.1 1033.87  4952.1 1035.05
  4961.3 1033.40  4969.8 1033.30  4970.3 1030.30  4976.9 1030.30  4977.4 1033.30
  5020.1 1035.88  5025.9 1037.22  5048.2 1037.12  5053.8 1038.03  5070.4 1038.28
  5114.8 1036.44  5131.4 1039.56  5137.0 1038.90  5153.6 1043.23  5159.2 1041.83
  5175.8 1045.12  5181.4 1044.39  5198.0 1047.31  5203.6 1046.98  5278.5 1051.70
#Mann=3,-1,0
  4222.7    0.05       0  4969.8    0.03       0  4977.4    0.05       0
Bank Sta=4969.8,4977.4
Exp/Cntr=0.3,0.1

Type RM Length L Ch R = 1,11593,495,495,495
BEGIN DESCRIPTION:
REED CREEK 24.0
END DESCRIPTION:
XS GIS Cut Line= 3
      2839455.67     10267703.13      2839640.50     10267507.00
      2839705.66     10267403.15
#Sta/Elev= 30
  4730.5 1041.54  4808.4 1040.45  4850.9 1041.11  4857.8 1040.38  4865.1 1040.45
  4871.9 1039.85  4886.1 1039.77  4900.2 1039.98  4914.4 1040.65  4928.6 1040.46
  4950.0 1035.69  4964.1 1033.95  4977.9 1031.01  4985.2 1030.69  4988.2 1029.94
  4988.7 1026.94  4995.4 1026.94  4995.9 1029.94  4999.2 1030.46  5005.4 1030.30
  5014.8 1031.99  5020.7 1032.26  5028.2 1033.13  5036.0 1032.85  5041.9 1033.52
  5057.3 1033.54  5063.6 1034.41  5078.5 1037.80  5093.8 1043.16  5122.6 1045.25
#Mann=3,-1,0
  4730.5    0.05       0  4988.2    0.03       0  4995.9    0.05       0
Bank Sta=4988.2,4995.9
Exp/Cntr=0.3,0.1

Type RM Length L Ch R = 1,11098,474,474,474
BEGIN DESCRIPTION:
REED CREEK 23.0
END DESCRIPTION:
XS GIS Cut Line= 3
      2840155.67     10267953.08      2840049.50     10267663.00
      2840005.68     10267553.11
#Sta/Elev= 30
  4691.1 1048.60  4714.0 1047.20  4736.8 1046.29  4762.0 1043.48  4767.4 1043.68
  4776.3 1042.47  4786.9 1041.97  4792.6 1040.78  4817.4 1039.62  4840.1 1038.39
  4848.3 1036.78  4853.6 1037.25  4861.4 1035.43  4904.0 1031.54  4909.3 1031.79
  4914.7 1030.46  4947.2 1028.87  4965.0 1027.70  4995.6 1027.75  5010.6 1026.56
  5025.3 1026.74  5026.0 1026.25  5026.5 1023.25  5037.9 1023.25  5038.4 1026.25
  5042.9 1027.05  5049.6 1027.14  5054.2 1029.34  5086.0 1036.99  5118.3 1038.64
#Mann=7,-1,0
  4691.1    0.05       0  4714.0    0.12       0  4817.4    0.05       0
  4947.2    0.12       0  5026.0    0.07       0  5038.4    0.12       0
  5054.2    0.05       0
Bank Sta=5026,5038.4
Exp/Cntr=0.3,0.1

Type RM Length L Ch R = 1,10624,448,448,448
BEGIN DESCRIPTION:
REED CREEK 22.0
END DESCRIPTION:
XS GIS Cut Line= 3
      2840305.70     10267953.07      2840483.50     10267573.00
      2840255.67     10267403.10
#Sta/Elev= 30
  4580.4 1048.78  4617.1 1046.56  4663.1 1043.05  4685.9 1039.90  4691.4 1040.28
  4805.6 1034.41  4822.9 1029.91  4828.5 1029.96  4834.3 1028.75  4874.1 1029.05
  4971.0 1027.97  4988.3 1024.19  5020.4 1023.31  5020.5 1022.51  5021.0 1019.51
  5032.4 1019.51  5032.9 1022.51  5055.9 1022.89  5062.1 1025.06  5070.5 1025.83
  5076.7 1029.56  5091.3 1030.73  5097.6 1034.45  5103.0 1034.54  5112.2 1036.26
  5120.5 1035.80  5126.8 1036.91  5147.6 1037.58  5166.1 1037.14  5284.2 1038.07
#Mann=6,-1,0
  4580.4    0.12       0  4617.1    0.05       0  5020.5    0.05       0
  5032.9    0.05       0  5103.0    0.12       0  5166.1    0.05       0
Bank Sta=5020.5,5032.9
Exp/Cntr=0.3,0.1

Type RM Length L Ch R = 1,10176,478,478,478
BEGIN DESCRIPTION:
REED CREEK 21.0
END DESCRIPTION:
XS GIS Cut Line= 3
      2840855.68     10267803.11      2840924.50     10267503.00
      2840605.70     10267103.13
#Sta/Elev= 30
  4692.1 1038.43  4716.1 1038.56  4743.4 1036.88  4759.0 1035.26  4849.9 1032.09
  4887.0 1028.66  4892.8 1027.59  4897.9 1027.86  4935.7 1025.19  4969.1 1025.21
  4983.4 1022.12  4983.9 1019.12  4995.4 1019.12  4995.9 1022.12  5041.4 1022.99
  5055.8 1024.59  5063.8 1027.09  5070.2 1029.84  5076.6 1029.72  5091.1 1033.91
  5099.1 1034.75  5127.7 1034.25  5155.1 1035.16  5177.5 1035.17  5255.6 1034.20
  5383.5 1034.93  5447.5 1036.90  5454.6 1037.80  5489.8 1039.17  5511.4 1041.85
#Mann=3,-1,0
  4692.1    0.05       0  4983.4    0.05       0  4995.9    0.05       0
Bank Sta=4983.4,4995.9
Exp/Cntr=0.3,0.1

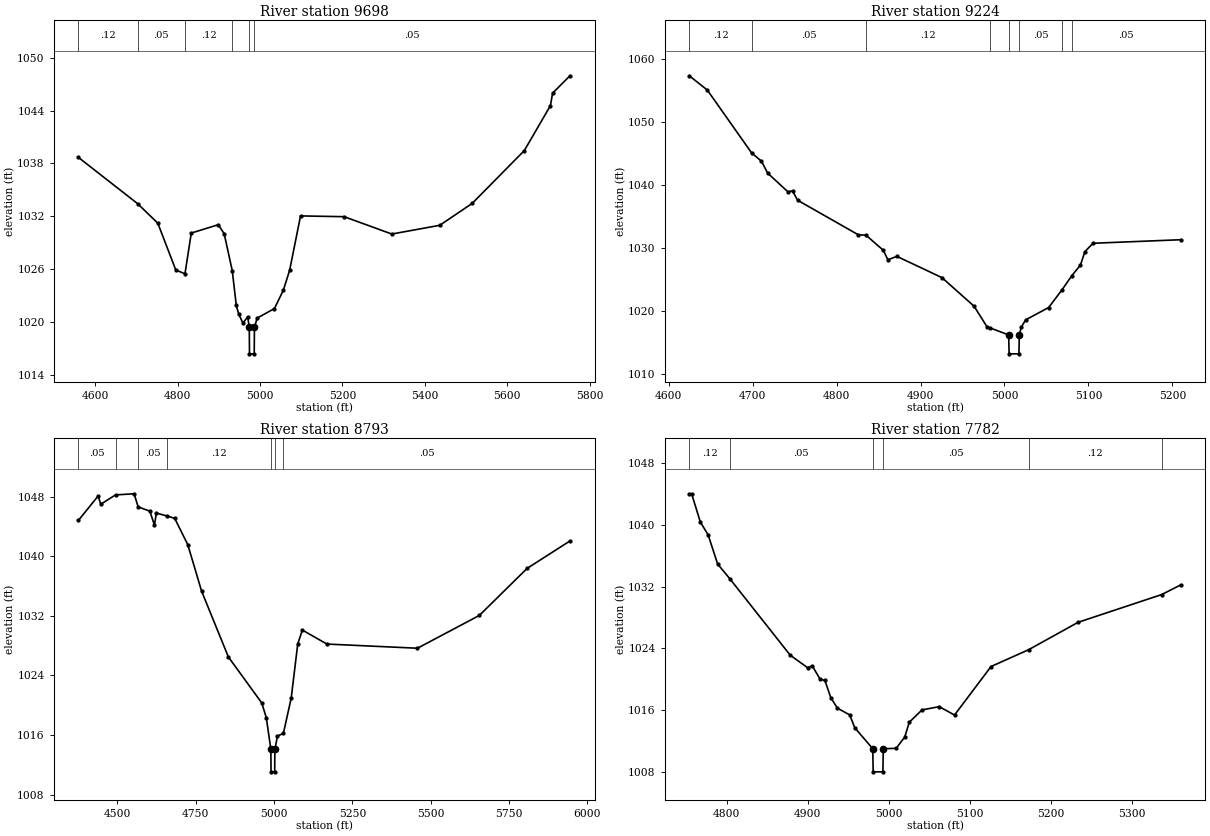
Type RM Length L Ch R = 1,9698,474,474,474
BEGIN DESCRIPTION:
REED CREEK 20.0
END DESCRIPTION:
XS GIS Cut Line= 3
      2841605.69     10267803.12      2841393.25     10267417.00
      2841155.68     10266703.09
#Sta/Elev= 30
  4559.3 1038.69  4703.0 1033.43  4752.0 1031.21  4795.6 1025.89  4817.9 1025.46
  4833.2 1030.09  4898.8 1031.04  4913.1 1030.01  4932.7 1025.81  4942.4 1021.87
  4948.1 1020.92  4958.5 1019.85  4970.2 1020.57  4974.0 1019.36  4974.5 1016.36
  4986.0 1016.36  4986.5 1019.36  4993.0 1020.42  5035.1 1021.51  5056.8 1023.61
  5072.0 1025.87  5098.4 1032.04  5204.3 1031.95  5319.9 1029.98  5436.2 1030.97
  5515.0 1033.46  5641.6 1039.47  5704.9 1044.57  5710.2 1045.99  5752.4 1047.97
#Mann=6,-1,0
  4559.3    0.12       0  4703.0    0.05       0  4817.9    0.12       0
  4932.7    0.05       0  4974.0    0.05       0  4986.5    0.05       0
Bank Sta=4974,4986.5
Exp/Cntr=0.3,0.1

Type RM Length L Ch R = 1,9224,431,431,431
BEGIN DESCRIPTION:
REED CREEK 19.0
END DESCRIPTION:
XS GIS Cut Line= 3
      2842155.68     10267353.11      2841806.50     10267215.00
      2841605.72     10267153.12
#Sta/Elev= 30
  4624.5 1057.28  4646.0 1055.01  4698.8 1045.03  4710.5 1043.72  4717.8 1041.84
  4742.1 1038.85  4747.5 1039.03  4753.5 1037.53  4825.9 1032.04  4835.0 1031.98
  4855.6 1029.59  4861.1 1028.08  4871.8 1028.62  4925.6 1025.24  4963.8 1020.70
  4979.4 1017.40  4982.6 1017.28  5005.0 1016.15  5005.5 1013.15  5017.2 1013.15
  5017.7 1016.15  5020.0 1017.38  5025.2 1018.54  5052.6 1020.50  5068.7 1023.34
  5080.1 1025.53  5090.5 1027.24  5095.8 1029.37  5105.5 1030.70  5210.1 1031.26
#Mann=8,-1,0
  4624.5    0.12       0  4698.8    0.05       0  4835.0    0.12       0
  4982.6    0.05       0  5005.0    0.05       0  5017.7    0.05       0
  5068.7    0.12       0  5080.1    0.05       0
Bank Sta=5005,5017.7
Exp/Cntr=0.3,0.1

Type RM Length L Ch R = 1,8793,1011,1011,1011
BEGIN DESCRIPTION:
Mapping XS 6f2454f5
END DESCRIPTION:
XS GIS Cut Line= 3
      2842445.94     10267381.48      2841980.27     10266750.58
      2841244.21     10266480.19
#Sta/Elev= 30
  4376.1 1044.81  4438.9 1048.08  4447.4 1046.98  4494.6 1048.23  4553.8 1048.38
  4566.6 1046.62  4603.9 1046.05  4618.6 1044.18  4624.8 1045.79  4657.8 1045.41
  4683.3 1045.08  4725.0 1041.55  4768.9 1035.33  4854.5 1026.48  4961.0 1020.31
  4975.6 1018.31  4990.1 1014.06  4990.6 1011.06  5002.3 1011.06  5002.8 1014.06
  5011.1 1015.86  5030.0 1016.22  5055.0 1020.96  5075.8 1028.22  5090.5 1030.09
  5168.9 1028.21  5457.8 1027.65  5655.1 1032.05  5807.5 1038.36  5944.4 1042.05
#Mann=7,-1,0
  4376.1    0.05       0  4494.6    0.12       0  4566.6    0.05       0
  4657.8    0.12       0  4990.1    0.07       0  5002.8    0.12       0
  5030.0    0.05       0
Bank Sta=4990.1,5002.8
Exp/Cntr=0.3,0.1

Type RM Length L Ch R = 1,7782,495,495,495
BEGIN DESCRIPTION:
REED CREEK 16.0
END DESCRIPTION:
XS GIS Cut Line= 3
      2842555.71     10266053.13      2842344.50     10265927.00
      2842005.64     10265803.10
#Sta/Elev= 30
  4754.0 1044.06  4756.9 1044.06  4767.6 1040.40  4777.3 1038.72  4789.0 1034.94
  4803.9 1033.05  4878.6 1023.11  4900.0 1021.49  4905.8 1021.73  4915.5 1019.99
  4921.4 1019.83  4928.7 1017.59  4936.9 1016.23  4952.0 1015.36  4958.3 1013.69
  4980.5 1010.97  4981.0 1007.97  4993.0 1007.97  4993.5 1010.97  5009.4 1011.02
  5020.0 1012.50  5025.6 1014.41  5041.3 1016.01  5062.6 1016.43  5081.4 1015.34
  5126.5 1021.64  5172.9 1023.82  5234.0 1027.38  5337.2 1030.98  5360.8 1032.24
#Mann=6,-1,0
  4754.0    0.12       0  4803.9    0.05       0  4980.5    0.03       0
  4993.5    0.05       0  5172.9    0.12       0  5337.2    0.05       0
Bank Sta=4980.5,4993.5
Exp/Cntr=0.3,0.1