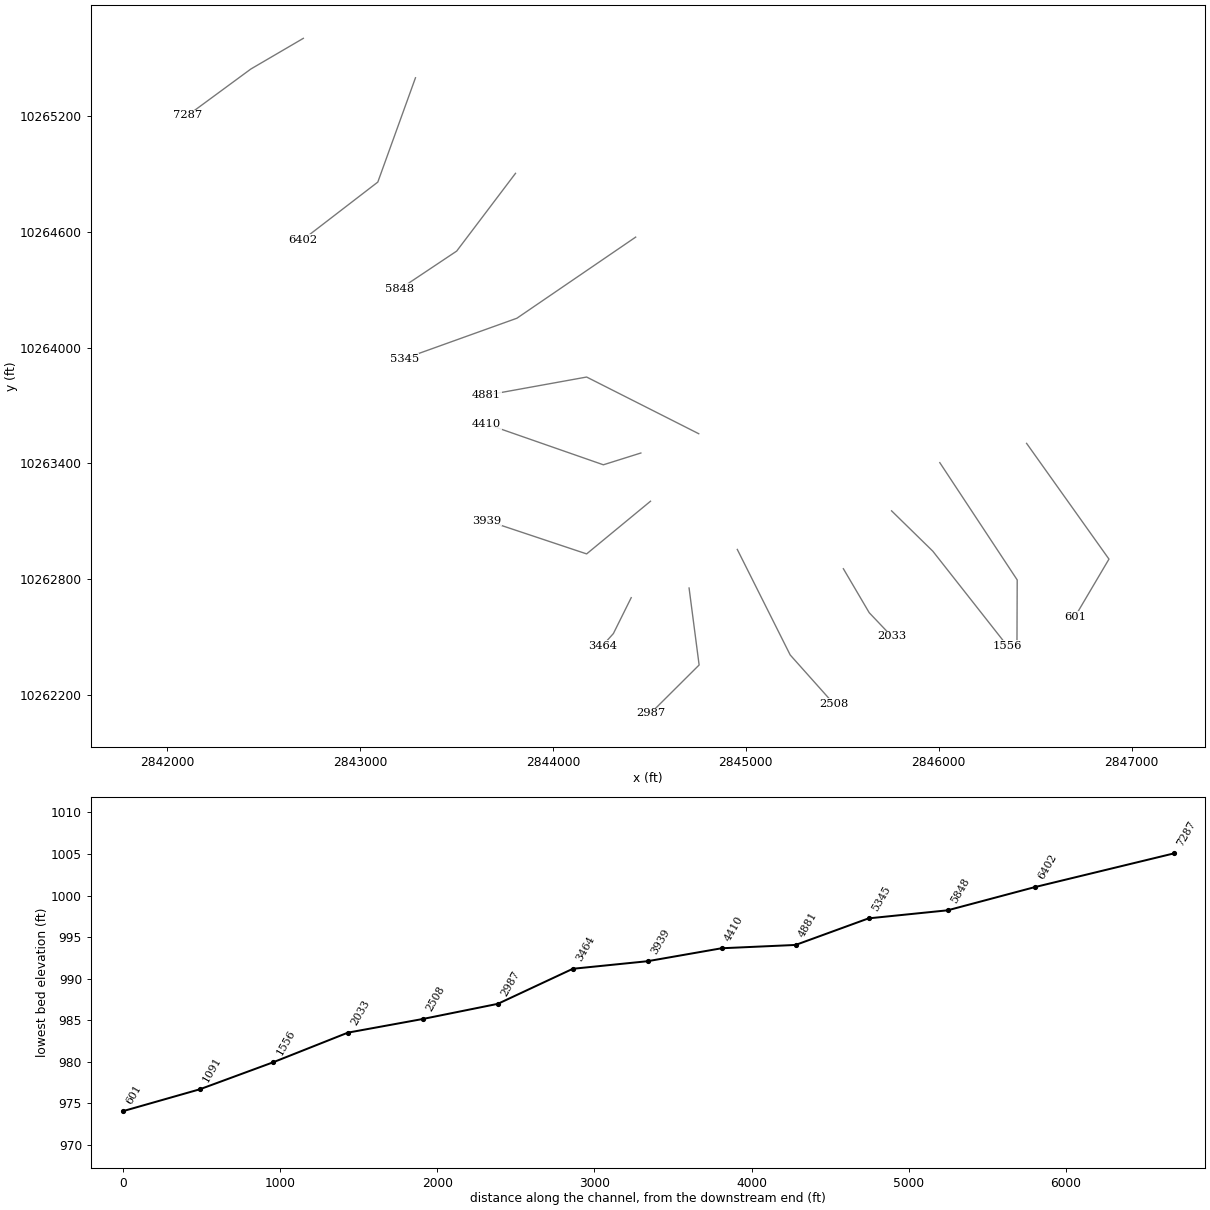
HEC-RAS study REED CREEK.prj: REED CREEK Base Level Engineering

--- REED CREEK.g01 (geometry) --- (continued)

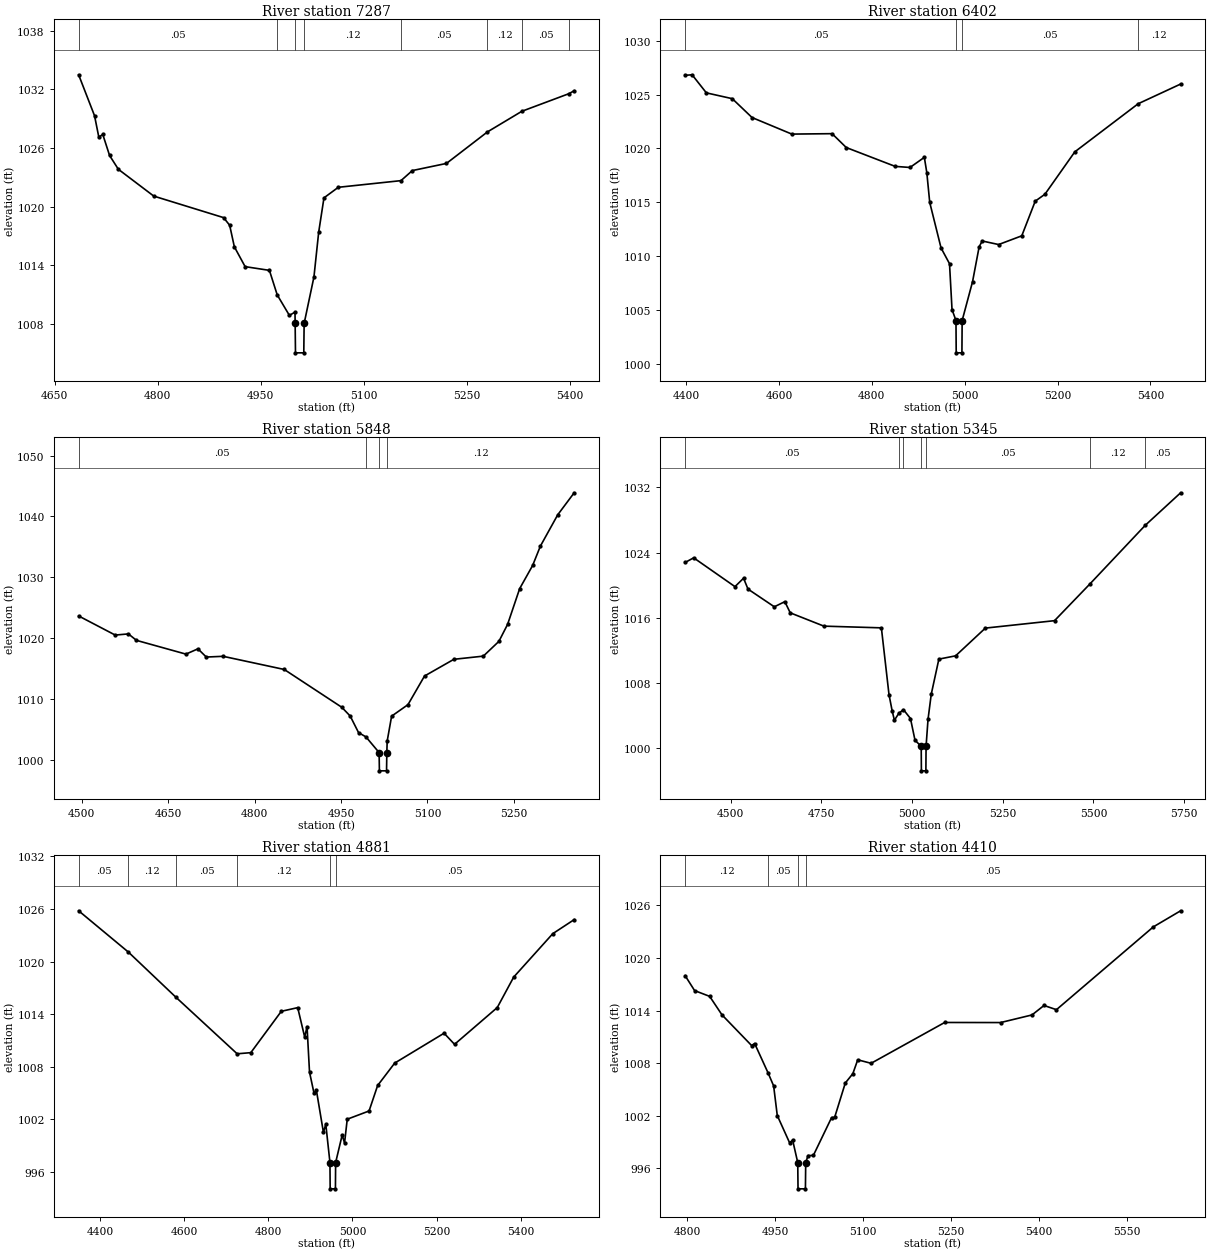
Type RM Length L Ch R = 1,7287,885,885,885
BEGIN DESCRIPTION:
REED CREEK 15.0
END DESCRIPTION:
XS GIS Cut Line= 3
      2842705.70     10265603.12      2842433.50     10265444.00
      2842105.69     10265203.11
#Sta/Elev= 30
  4684.7 1033.49  4707.9 1029.30  4714.1 1027.12  4719.9 1027.39  4729.8 1025.24
  4742.6 1023.83  4794.2 1021.09  4895.9 1018.89  4904.8 1018.11  4911.6 1015.91
  4927.3 1013.88  4962.7 1013.50  4974.1 1010.99  4991.8 1008.90  5000.0 1009.23
  5000.2 1008.07  5000.7 1005.07  5012.8 1005.07  5013.3 1008.07  5027.6 1012.83
  5034.5 1017.40  5042.2 1020.91  5063.1 1021.99  5154.4 1022.67  5171.0 1023.70
  5220.7 1024.43  5280.4 1027.65  5330.6 1029.76  5399.2 1031.56  5406.8 1031.86
#Mann=8,-1,0
  4684.7    0.05       0  4974.1    0.12       0  5000.2    0.07       0
  5013.3    0.12       0  5154.4    0.05       0  5280.4    0.12       0
  5330.6    0.05       0  5399.2    0.12       0
Bank Sta=5000.2,5013.3
Exp/Cntr=0.3,0.1

Type RM Length L Ch R = 1,6402,554,554,554
BEGIN DESCRIPTION:
Mapping XS e59d9107
END DESCRIPTION:
XS GIS Cut Line= 3
      2843287.13     10265398.64      2843091.86     10264857.87
      2842701.76     10264557.80
#Sta/Elev= 30
  4397.9 1026.79  4413.0 1026.84  4443.7 1025.16  4499.5 1024.62  4542.0 1022.87
  4627.7 1021.33  4714.4 1021.37  4745.0 1020.08  4850.3 1018.33  4882.2 1018.23
  4913.1 1019.17  4918.4 1017.75  4924.7 1014.98  4949.1 1010.75  4967.3 1009.29
  4972.7 1005.03  4981.2 1004.01  4981.7 1001.01  4994.0 1001.01  4994.5 1004.01
  5016.9 1007.62  5031.1 1010.86  5037.7 1011.40  5073.1 1011.07  5122.9 1011.88
  5151.9 1015.10  5172.7 1015.74  5237.1 1019.68  5373.6 1024.15  5465.0 1025.98
#Mann=4,-1,0
  4397.9    0.05       0  4981.2    0.05       0  4994.5    0.05       0
  5373.6    0.12       0
Bank Sta=4981.2,4994.5
Exp/Cntr=0.3,0.1

Type RM Length L Ch R = 1,5848,503,503,503
BEGIN DESCRIPTION:
REED CREEK 12.0
END DESCRIPTION:
XS GIS Cut Line= 3
      2843805.71     10264903.15      2843500.75     10264500.00
      2843205.70     10264303.12
#Sta/Elev= 30
  4494.5 1023.66  4558.0 1020.52  4580.9 1020.71  4594.9 1019.65  4680.8 1017.39
  4701.6 1018.26  4716.1 1016.91  4745.3 1017.03  4851.4 1014.87  4951.3 1008.66
  4965.9 1007.22  4980.4 1004.50  4993.3 1003.79  5016.1 1001.22  5016.6  998.22
  5029.0  998.22  5029.5 1001.22  5030.1 1003.10  5037.8 1007.20  5066.2 1009.09
  5094.9 1013.79  5145.9 1016.54  5197.0 1017.06  5224.0 1019.48  5239.1 1022.27
  5260.1 1028.15  5282.6 1031.95  5296.1 1035.14  5326.2 1040.28  5354.7 1043.89
#Mann=4,-1,0
  4494.5    0.05       0  4993.3    0.12       0  5016.1    0.07       0
  5029.5    0.12       0
Bank Sta=5016.1,5029.5
Exp/Cntr=0.3,0.1

Type RM Length L Ch R = 1,5345,464,464,464
BEGIN DESCRIPTION:
Mapping XS cc71b661
END DESCRIPTION:
XS GIS Cut Line= 3
      2844428.80     10264572.49      2843812.89     10264151.86
      2843228.91     10263942.23
#Sta/Elev= 30
  4374.1 1022.78  4397.8 1023.35  4511.6 1019.82  4535.3 1020.85  4547.5 1019.52
  4620.1 1017.35  4649.1 1017.98  4664.0 1016.61  4756.8 1014.98  4915.3 1014.77
  4936.3 1006.59  4945.1 1004.58  4951.2 1003.45  4963.1 1004.28  4976.1 1004.75
  4995.5 1003.66  5008.0 1001.00  5025.1 1000.25  5025.6  997.25  5038.0  997.25
  5038.5 1000.25  5043.9 1003.56  5052.8 1006.64  5073.8 1010.94  5119.9 1011.34
  5202.0 1014.74  5392.7 1015.65  5490.5 1020.16  5642.5 1027.32  5740.4 1031.32
#Mann=7,-1,0
  4374.1    0.05       0  4963.1    0.12       0  4976.1    0.05       0
  5025.1    0.05       0  5038.5    0.05       0  5490.5    0.12       0
  5642.5    0.05       0
Bank Sta=5025.1,5038.5
Exp/Cntr=0.3,0.1

Type RM Length L Ch R = 1,4881,471,471,471
BEGIN DESCRIPTION:
REED CREEK 10.0
END DESCRIPTION:
XS GIS Cut Line= 3
      2844755.72     10263553.10      2844174.50     10263847.00
      2843655.73     10263753.12
#Sta/Elev= 30
  4348.7 1025.80  4467.1 1021.08  4580.2 1015.92  4725.7 1009.47  4758.2 1009.60
  4830.7 1014.32  4869.7 1014.74  4886.3 1011.38  4891.9 1012.58  4897.8 1007.38
  4908.6 1004.94  4914.2 1005.29  4930.9 1000.49  4936.5 1001.43  4946.4  997.05
  4946.9  994.05  4959.4  994.05  4959.9  997.05  4975.5 1000.20  4981.1  999.28
  4987.5 1002.00  5039.4 1002.94  5059.8 1005.85  5100.4 1008.41  5217.8 1011.82
  5242.7 1010.55  5344.3 1014.75  5383.4 1018.23  5476.4 1023.19  5527.2 1024.79
#Mann=6,-1,0
  4348.7    0.05       0  4467.1    0.12       0  4580.2    0.05       0
  4725.7    0.12       0  4946.4    0.05       0  4959.9    0.05       0
Bank Sta=4946.4,4959.9
Exp/Cntr=0.3,0.1

Type RM Length L Ch R = 1,4410,471,471,471
BEGIN DESCRIPTION:
REED CREEK 9.0
END DESCRIPTION:
XS GIS Cut Line= 3
      2844455.67     10263453.11      2844261.25     10263392.00
      2843655.69     10263603.11
#Sta/Elev= 30
  4796.2 1017.99  4812.4 1016.28  4838.1 1015.62  4859.1 1013.51  4909.6 1010.01
  4914.8 1010.24  4937.8 1006.87  4947.2 1005.40  4953.4 1002.02  4974.4  998.91
  4979.6  999.21  4988.3  996.65  4988.8  993.65  5001.4  993.65  5001.9  996.65
  5005.9  997.45  5014.9  997.46  5046.0 1001.78  5051.2 1001.80  5069.4 1005.73
  5082.3 1006.80  5090.6 1008.38  5113.4 1007.98  5238.9 1012.64  5334.2 1012.63
  5387.8 1013.50  5408.3 1014.58  5429.5 1014.10  5594.7 1023.55  5641.3 1025.39
#Mann=4,-1,0
  4796.2    0.12       0  4937.8    0.05       0  4988.3    0.05       0
  5001.9    0.05       0
Bank Sta=4988.3,5001.9
Exp/Cntr=0.3,0.1

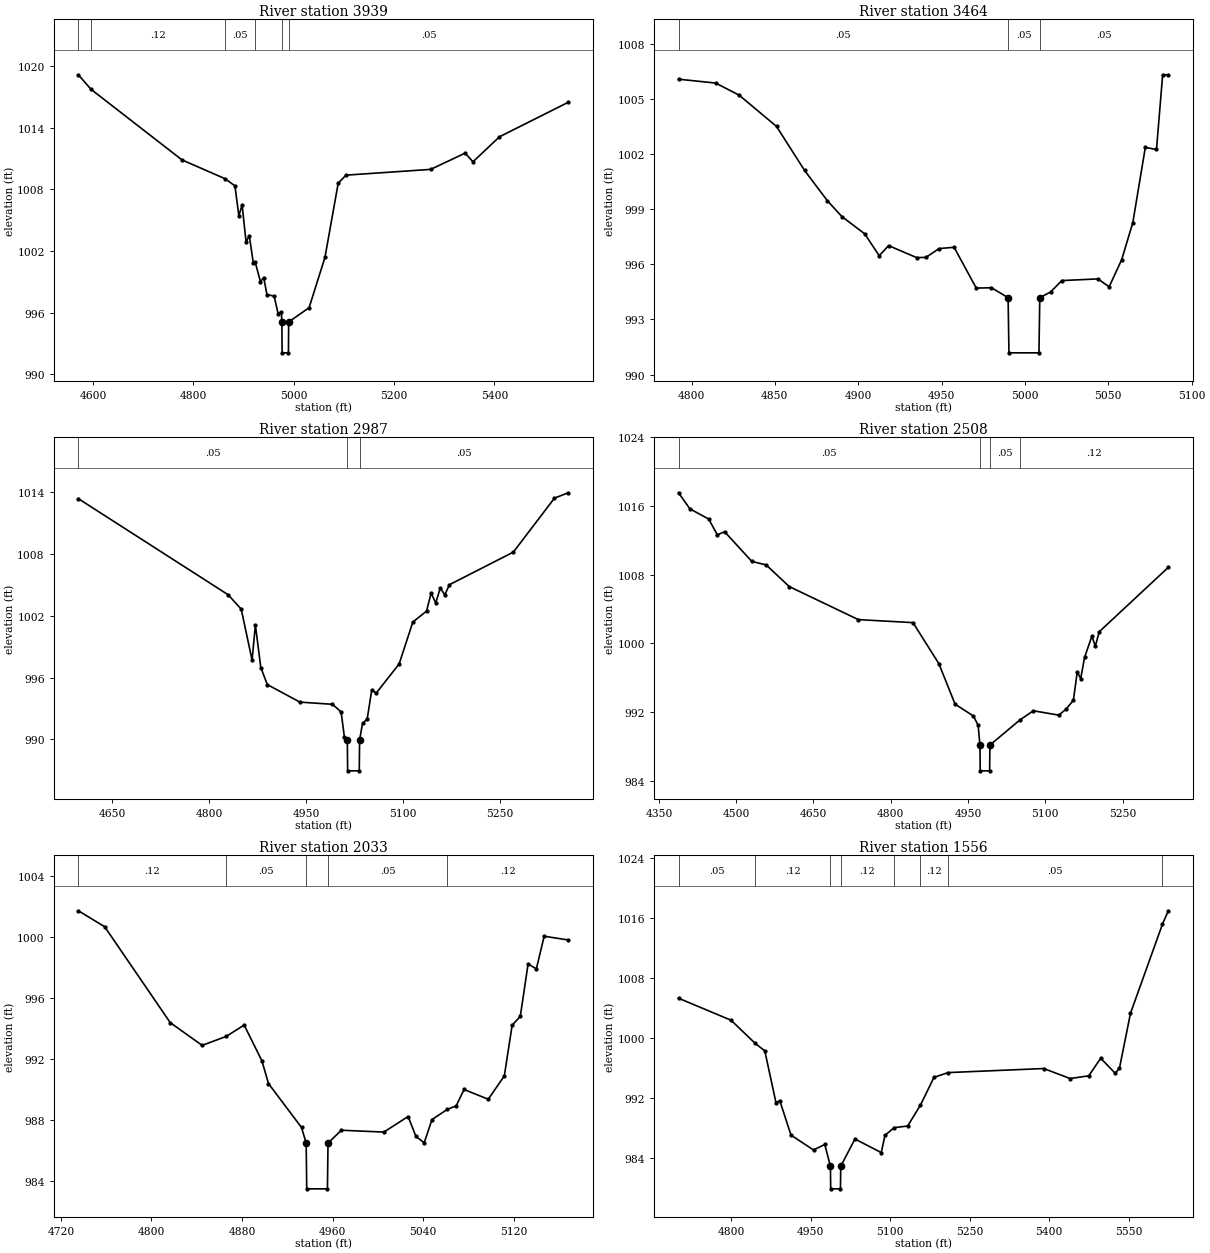
Type RM Length L Ch R = 1,3939,475,475,475
BEGIN DESCRIPTION:
REED CREEK 8.0
END DESCRIPTION:
XS GIS Cut Line= 3
      2844505.71     10263203.13      2844174.50     10262930.00
      2843655.72     10263103.10
#Sta/Elev= 30
  4570.7 1019.13  4595.9 1017.72  4777.3 1010.85  4862.8 1009.03  4882.8 1008.33
  4890.6 1005.41  4897.1 1006.48  4905.0 1002.85  4911.4 1003.50  4919.3 1000.85
  4923.0 1000.94  4933.6  999.02  4940.1  999.41  4946.6  997.76  4960.9  997.60
  4968.8  995.90  4975.3  996.08  4976.3  995.09  4976.8  992.09  4989.4  992.09
  4989.9  995.09  5030.6  996.48  5062.2 1001.37  5088.6 1008.59  5104.2 1009.37
  5272.8 1009.93  5341.5 1011.51  5357.2 1010.67  5410.0 1013.10  5546.9 1016.45
#Mann=6,-1,0
  4570.7    0.05       0  4595.9    0.12       0  4862.8    0.05       0
  4923.0    0.12       0  4976.3    0.03       0  4989.9    0.05       0
Bank Sta=4976.3,4989.9
Exp/Cntr=0.3,0.1

Type RM Length L Ch R = 1,3464,477,477,477
BEGIN DESCRIPTION:
REED CREEK 7.0
END DESCRIPTION:
XS GIS Cut Line= 3
      2844405.68     10262703.11      2844313.25     10262517.00
      2844255.68     10262453.11
#Sta/Elev= 30
  4792.2 1006.06  4814.5 1005.85  4828.6 1005.19  4851.0 1003.49  4867.8 1001.10
  4881.5  999.45  4890.2  998.59  4903.9  997.65  4912.6  996.46  4918.2  997.01
  4935.0  996.36  4940.6  996.37  4948.5  996.85  4957.5  996.92  4970.8  994.70
  4979.9  994.72  4989.9  994.18  4990.4  991.18  5008.4  991.18  5008.9  994.18
  5015.4  994.49  5022.1  995.11  5043.8  995.20  5050.5  994.77  5058.0  996.24
  5064.7  998.26  5072.2 1002.35  5078.9 1002.24  5082.6 1006.30  5086.0 1006.30
#Mann=3,-1,0
  4792.2    0.05       0  4989.9    0.05       0  5008.9    0.05       0
Bank Sta=4989.9,5008.9
Exp/Cntr=0.3,0.1

Type RM Length L Ch R = 1,2987,479,479,479
BEGIN DESCRIPTION:
REED CREEK 6.0
END DESCRIPTION:
XS GIS Cut Line= 3
      2844705.68     10262753.12      2844757.75     10262354.00
      2844505.71     10262103.14
#Sta/Elev= 30
  4597.5 1013.34  4829.5 1004.02  4849.6 1002.63  4866.4  997.69  4871.5 1001.10
  4879.9  996.97  4890.0  995.32  4940.4  993.62  4990.8  993.41  5004.2  992.67
  5009.2  990.27  5013.8  989.96  5014.3  986.96  5032.3  986.96  5032.8  989.96
  5037.4  991.58  5044.5  991.96  5051.6  994.79  5058.7  994.51  5094.0  997.32
  5115.2 1001.38  5136.4 1002.44  5143.5 1004.19  5150.6 1003.23  5157.7 1004.68
  5164.7 1004.01  5171.8 1005.00  5270.8 1008.16  5334.4 1013.39  5355.6 1013.91
#Mann=3,-1,0
  4597.5    0.05       0  5013.8    0.03       0  5032.8    0.05       0
Bank Sta=5013.8,5032.8
Exp/Cntr=0.3,0.1

Type RM Length L Ch R = 1,2508,475,475,475
BEGIN DESCRIPTION:
REED CREEK 5.0
END DESCRIPTION:
XS GIS Cut Line= 3
      2844955.70     10262953.09      2845230.00     10262406.00
      2845455.65     10262153.15
#Sta/Elev= 30
  4388.0 1017.53  4410.3 1015.65  4446.6 1014.47  4463.4 1012.63  4477.5 1012.99
  4530.4 1009.53  4558.3 1009.12  4603.0 1006.60  4737.1 1002.75  4843.2 1002.40
  4893.5  997.61  4924.9  992.90  4960.5  991.52  4969.7  990.44  4973.2  988.13
  4973.7  985.13  4992.0  985.13  4992.5  988.13  5050.6  991.05  5076.9  992.13
  5126.2  991.62  5140.4  992.32  5154.6  993.35  5162.1  996.66  5168.8  995.88
  5176.3  998.34  5190.5 1000.83  5197.2  999.65  5204.8 1001.34  5338.9 1008.84
#Mann=4,-1,0
  4388.0    0.05       0  4973.2    0.05       0  4992.5    0.05       0
  5050.6    0.12       0
Bank Sta=4973.2,4992.5
Exp/Cntr=0.3,0.1

Type RM Length L Ch R = 1,2033,477,477,477
BEGIN DESCRIPTION:
REED CREEK 4.0
END DESCRIPTION:
XS GIS Cut Line= 3
      2845505.68     10262853.12      2845639.75     10262625.00
      2845755.67     10262503.13
#Sta/Elev= 30
  4735.4 1001.71  4758.6 1000.67  4816.6  994.38  4844.8  992.89  4866.1  993.48
  4881.9  994.22  4897.6  991.88  4903.4  990.39  4932.6  987.51  4936.7  986.49
  4937.2  983.49  4955.5  983.49  4956.0  986.49  4967.8  987.33  5005.4  987.21
  5026.8  988.23  5033.7  986.92  5041.0  986.51  5047.9  988.03  5061.3  988.69
  5069.3  988.93  5076.2  990.00  5097.6  989.36  5111.8  990.89  5118.7  994.21
  5125.9  994.79  5132.8  998.23  5140.1  997.90  5147.0 1000.04  5168.2  999.80
#Mann=5,-1,0
  4735.4    0.12       0  4866.1    0.05       0  4936.7    0.05       0
  4956.0    0.05       0  5061.3    0.12       0
Bank Sta=4936.7,4956
Exp/Cntr=0.3,0.1

Type RM Length L Ch R = 1,1556,465,465,465
BEGIN DESCRIPTION:
REED CREEK 3.0
END DESCRIPTION:
XS GIS Cut Line= 3
      2845755.67     10263153.13      2845969.50     10262944.00
      2846355.69     10262453.10
#Sta/Elev= 30
  4700.9 1005.31  4799.9 1002.38  4845.7  999.28  4863.6  998.30  4884.7  991.39
  4891.9  991.65  4913.0  987.07  4955.5  985.09  4976.7  985.82  4987.4  982.91
  4987.9  979.91  5006.3  979.91  5006.8  982.91  5033.6  986.55  5083.3  984.74
  5090.2  987.03  5107.4  988.06  5133.0  988.28  5157.2  991.07  5182.7  994.77
  5209.4  995.40  5389.6  995.94  5439.3  994.61  5474.6  994.97  5497.1  997.31
  5524.3  995.32  5532.4  995.96  5553.2 1003.29  5613.6 1015.19  5624.6 1016.96
#Mann=8,-1,0
  4700.9    0.05       0  4845.7    0.12       0  4987.4    0.07       0
  5006.8    0.12       0  5107.4    0.05       0  5157.2    0.12       0
  5209.4    0.05       0  5613.6    0.12       0
Bank Sta=4987.4,5006.8
Exp/Cntr=0.3,0.1

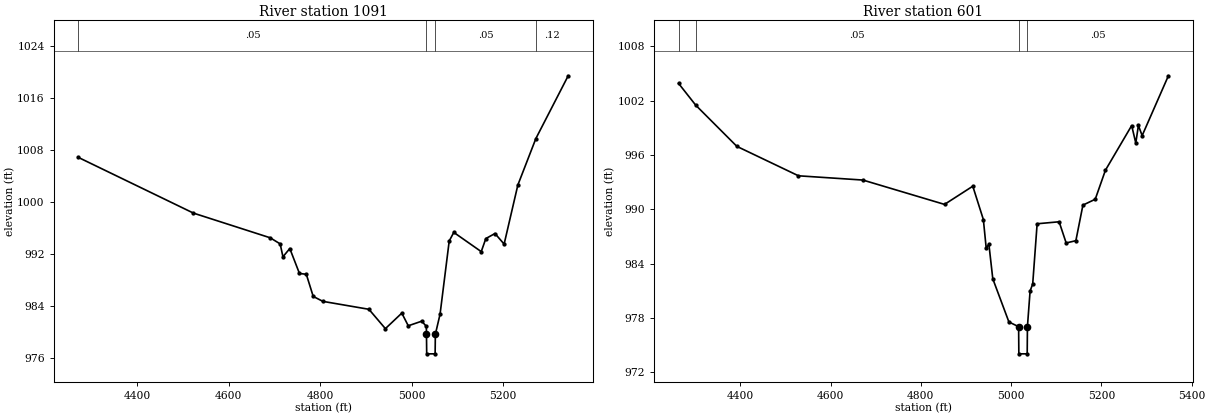
Type RM Length L Ch R = 1,1091,490,490,490
BEGIN DESCRIPTION:
REED CREEK 2.0
END DESCRIPTION:
XS GIS Cut Line= 3
      2846005.68     10263403.11      2846407.00     10262795.00
      2846405.68     10262453.10
#Sta/Elev= 30
  4271.4 1006.92  4523.0  998.34  4690.7  994.54  4712.5  993.60  4718.5  991.61
  4733.5  992.89  4754.6  989.05  4769.6  988.92  4784.7  985.51  4805.8  984.75
  4906.4  983.53  4942.4  980.55  4978.3  982.94  4992.4  980.99  5021.9  981.70
  5031.9  980.90  5032.2  979.67  5032.7  976.67  5051.1  976.67  5051.6  979.67
  5061.9  982.78  5081.9  994.05  5091.9  995.37  5151.9  992.41  5161.9  994.42
  5181.9  995.20  5201.9  993.57  5231.9 1002.67  5271.3 1009.83  5341.9 1019.49
#Mann=4,-1,0
  4271.4    0.05       0  5032.2    0.05       0  5051.6    0.05       0
  5271.3    0.12       0
Bank Sta=5032.2,5051.6
Exp/Cntr=0.3,0.1

Type RM Length L Ch R = 1,601,0,0,0
BEGIN DESCRIPTION:
REED CREEK 1.0
END DESCRIPTION:
XS GIS Cut Line= 3
      2846455.66     10263503.15      2846882.75     10262903.00
      2846705.66     10262603.08
#Sta/Elev= 30
  4263.4 1003.91  4301.5 1001.50  4392.6  996.95  4529.0  993.70  4671.7  993.23
  4852.5  990.54  4915.1  992.55  4938.5  988.87  4944.7  985.76  4950.8  986.12
  4959.4  982.32  4995.1  977.55  5016.6  977.03  5017.1  974.03  5035.6  974.03
  5036.1  977.03  5042.0  980.97  5047.8  981.75  5057.6  988.40  5106.3  988.62
  5121.9  986.28  5143.4  986.53  5159.0  990.46  5186.3  991.11  5208.9  994.32
  5267.0  999.25  5276.1  997.32  5281.9  999.26  5290.2  998.14  5348.3 1004.75
#Mann=4,-1,0
  4263.4    0.12       0  4301.5    0.05       0  5016.6    0.03       0
  5036.1    0.05       0
Bank Sta=5016.6,5036.1
Exp/Cntr=0.3,0.1

Chan Stop Cuts=-1