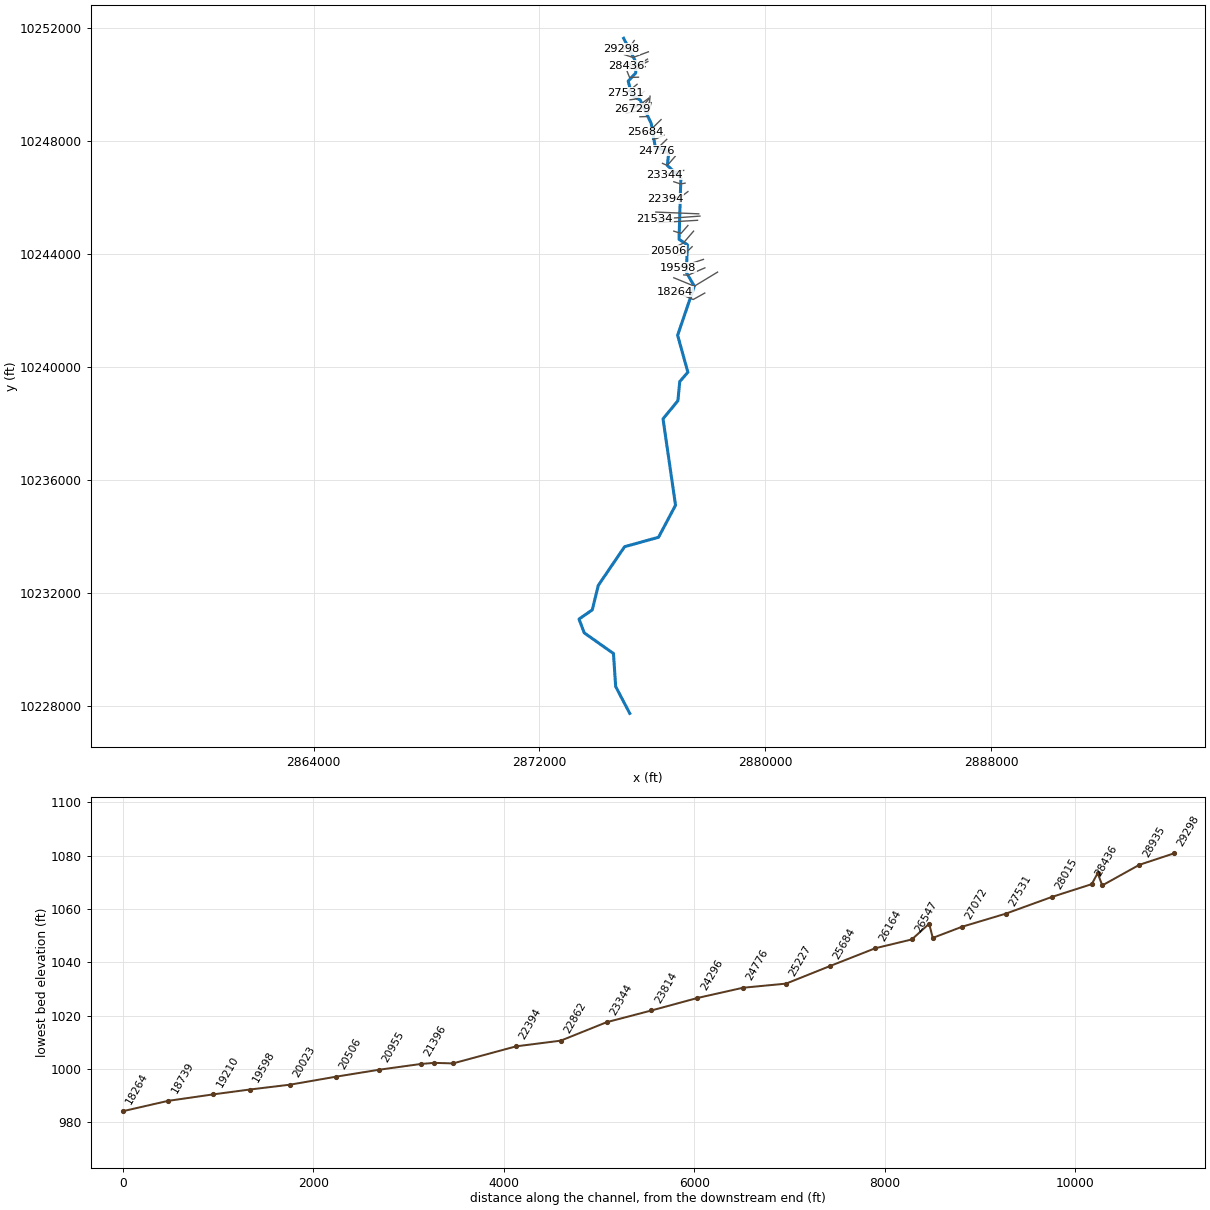
--- SANDY CREEK.prj (project) ---

Proj Title=SANDY CREEK Base Level Engineering
Current Plan=p01
Default Exp/Contr=0.3,0.1
English Units
Geom File=g01
Flow File=f01
Plan File=p01
BEGIN DESCRIPTION:
SANDY CREEK
END DESCRIPTION:

--- SANDY CREEK.p01 (plan) ---

Plan Title=Multiple Run
Short Identifier=Multiple
Geom File=g01
Flow File=f01
Subcritical Flow
K Sum by GR= 0
Std Step Tol= 0.01
Critical Tol= 0.01
Num of Std Step Trials= 20
Max Error Tol= 0.3
Flow Tol Ratio= 0.001
Split Flow NTrial= 30
Split Flow Tol= 0.02
Split Flow Ratio= 0.02
Log Output Level= 0
Friction Slope Method= 1
Unsteady Friction Slope Method= 2
Unsteady Bridges Friction Slope Method= 1
Parabolic Critical Depth
Global Vel Dist=  1 , 1 , 1
Global Log Level= 0
CheckData=True
Encroach Param= -1, 0, 0, 0
BEGIN DESCRIPTION:
Multiple Run
END DESCRIPTION:

--- SANDY CREEK.f01 (steady flow) ---

Flow Title=Multiple
Number of Profiles=7
Profile Names=10-year,25-year,50-year,1pct_min,100-year,1pct_plu,500-year
River Rch & RM= SANDY CREEK,Reach-1,29298
      71     138     216     113     340    1026     901
River Rch & RM= SANDY CREEK,Reach-1,18739
      74     147     231     121     365    1103     974
River Rch & RM= SANDY CREEK,Reach-1,15365
     166     358     589     319     964    2910    2739
River Rch & RM= SANDY CREEK,Reach-1,11029
     197     432     717     390    1179    3561    3391
River Rch & RM= SANDY CREEK,Reach-1,6797
     244     543     909     499    1506    4548    4389
Boundary for River Rch & Prof#=SANDY CREEK,Reach-1,1
Up Type=0
Dn Type=3
Dn Slope=0.005
Boundary for River Rch & Prof#=SANDY CREEK,Reach-1,2
Up Type=0
Dn Type=3
Dn Slope=0.005
Boundary for River Rch & Prof#=SANDY CREEK,Reach-1,3
Up Type=0
Dn Type=3
Dn Slope=0.005
Boundary for River Rch & Prof#=SANDY CREEK,Reach-1,4
Up Type=0
Dn Type=3
Dn Slope=0.005
Boundary for River Rch & Prof#=SANDY CREEK,Reach-1,5
Up Type=0
Dn Type=3
Dn Slope=0.005
Boundary for River Rch & Prof#=SANDY CREEK,Reach-1,6
Up Type=0
Dn Type=3
Dn Slope=0.005
Boundary for River Rch & Prof#=SANDY CREEK,Reach-1,7
Up Type=0
Dn Type=3
Dn Slope=0.005

--- SANDY CREEK.g01 (geometry) ---

Geom Title=Existing Conditions

River Reach=SANDY CREEK,Reach-1
Reach XY= 30
      2874979.75     10251630.00      2875413.00     10250792.00
      2875408.50     10250405.00      2875140.25     10250114.00
      2875274.25     10249615.00      2875565.75     10249444.00
      2875955.50     10248617.00      2876100.00     10247774.00
      2876580.75     10247621.00      2876526.00     10247129.00
      2877006.00     10246691.00      2876941.75     10244513.00
      2877238.50     10244322.00      2877199.75     10243345.00
      2877482.25     10242854.00      2876891.25     10241116.00
      2877254.25     10239807.00      2876966.75     10239479.00
      2876901.25     10238798.00      2876374.00     10238158.00
      2876817.00     10235099.00      2876215.50     10233965.00
      2875013.00     10233630.00      2874081.75     10232260.00
      2873868.25     10231392.00      2873399.25     10231068.00
      2873584.75     10230579.00      2874619.25     10229848.00
      2874698.00     10228678.00      2875195.25     10227729.00

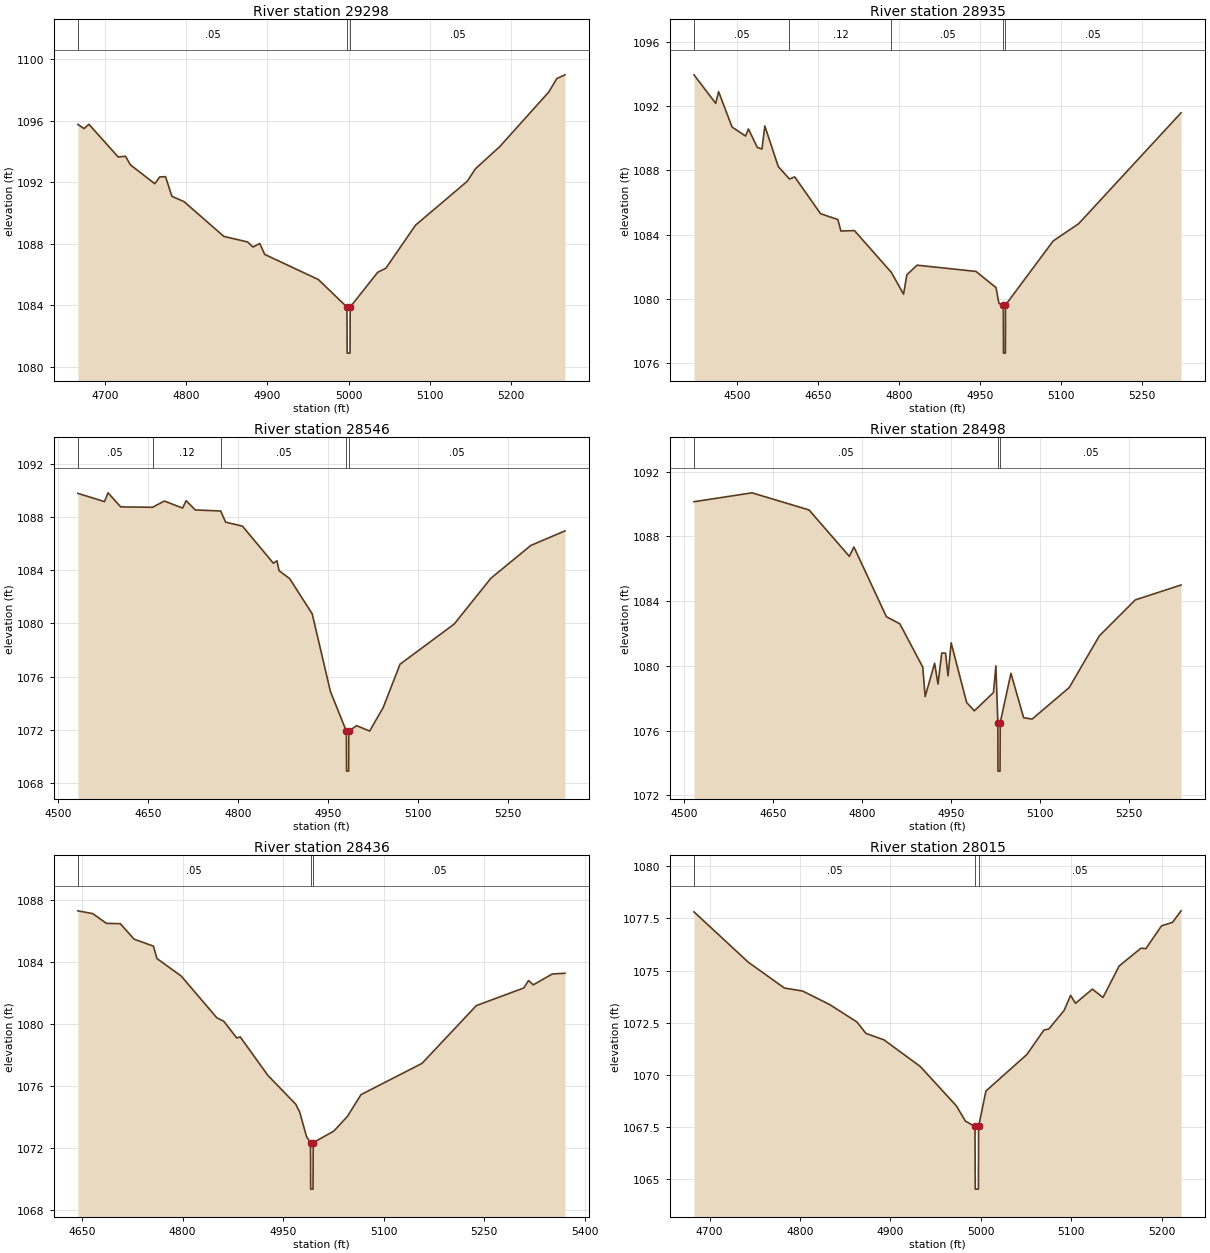
Type RM Length L Ch R = 1,29298,363,363,363
BEGIN DESCRIPTION:
SANDY CREEK 58.0
END DESCRIPTION:
XS GIS Cut Line= 3
      2875355.70     10251553.14      2875171.50     10251275.00
      2874905.70     10251253.11
#Sta/Elev= 30
  4666.4 1095.77  4674.0 1095.50  4680.0 1095.78  4716.1 1093.65  4725.1 1093.70
  4731.1 1093.14  4761.2 1091.91  4767.2 1092.35  4774.4 1092.37  4782.3 1091.09
  4797.3 1090.74  4846.3 1088.48  4875.5 1088.12  4882.3 1087.79  4890.6 1088.02
  4896.6 1087.31  4962.8 1085.67  4998.0 1083.88  4998.3 1080.88  5001.8 1080.88
  5002.0 1083.88  5035.9 1086.14  5046.0 1086.41  5082.5 1089.21  5146.3 1092.07
  5156.3 1092.88  5186.4 1094.33  5246.6 1097.87  5256.7 1098.76  5266.7 1099.00
#Mann=3,-1,0
  4666.4    0.05       0  4998.0    0.03       0  5002.0    0.05       0
Bank Sta=4998,5002
Exp/Cntr=0.3,0.1

Type RM Length L Ch R = 1,28935,389,389,389
BEGIN DESCRIPTION:
SANDY CREEK 57.0
END DESCRIPTION:
XS GIS Cut Line= 3
      2875855.71     10251153.12      2875311.75     10250951.00
      2875005.64     10251053.13
#Sta/Elev= 30
  4419.7 1093.97  4459.9 1092.19  4465.3 1092.92  4490.3 1090.71  4515.3 1090.15
  4520.6 1090.59  4537.1 1089.44  4545.7 1089.34  4551.0 1090.78  4576.0 1088.24
  4596.7 1087.47  4606.4 1087.60  4654.4 1085.30  4686.4 1084.94  4692.1 1084.22
  4717.1 1084.25  4785.6 1081.64  4808.2 1080.28  4814.4 1081.49  4833.2 1082.09
  4942.5 1081.70  4979.7 1080.69  4985.1 1079.70  4993.2 1079.60  4993.5 1076.60
  4997.0 1076.60  4997.2 1079.60  5085.6 1083.60  5132.9 1084.68  5322.7 1091.60
#Mann=5,-1,0
  4419.7    0.05       0  4596.7    0.12       0  4785.6    0.05       0
  4993.2    0.03       0  4997.2    0.05       0
Bank Sta=4993.2,4997.2
Exp/Cntr=0.3,0.1

Type RM Length L Ch R = 1,28546,48,48,48
BEGIN DESCRIPTION:
Mapping XS eef3483a
END DESCRIPTION:
XS GIS Cut Line= 4
      2875823.90     10250894.66      2875539.80     10250714.22
      2875424.64     10250648.96      2875114.26     10250798.40
#Sta/Elev= 30
  4532.4 1089.81  4576.8 1089.19  4582.8 1089.85  4603.9 1088.79  4657.0 1088.76
  4676.8 1089.23  4707.3 1088.70  4713.2 1089.26  4728.4 1088.56  4770.9 1088.48
  4779.1 1087.64  4807.2 1087.34  4858.9 1084.54  4864.8 1084.73  4868.4 1083.98
  4886.1 1083.38  4923.7 1080.73  4954.1 1074.88  4980.8 1071.87  4981.1 1068.87
  4984.6 1068.87  4984.8 1071.87  4997.8 1072.30  5019.6 1071.89  5042.2 1073.66
  5070.4 1076.93  5160.9 1079.96  5222.1 1083.41  5288.7 1085.88  5345.8 1086.98
#Mann=5,-1,0
  4532.4    0.05       0  4657.0    0.12       0  4770.9    0.05       0
  4980.8    0.05       0  4984.8    0.05       0
Bank Sta=4980.8,4984.8
Exp/Cntr=0.3,0.1

Type RM Length L Ch R = 1,28498,62,62,62
BEGIN DESCRIPTION:
Mapping XS 328af43f
END DESCRIPTION:
XS GIS Cut Line= 6
      2875839.25     10250810.20      2875493.74     10250645.12
      2875474.54     10250610.57      2875436.16     10250599.06
      2875355.54     10250618.25      2875105.99     10250737.27
#Sta/Elev= 30
  4516.7 1090.15  4614.6 1090.70  4710.9 1089.64  4778.9 1086.77  4786.6 1087.35
  4841.4 1083.04  4864.1 1082.60  4902.8 1079.92  4906.8 1078.10  4922.8 1080.16
  4928.5 1078.87  4934.8 1080.79  4941.2 1080.79  4945.4 1079.38  4950.7 1081.42
  4976.9 1077.73  4989.9 1077.22  5022.1 1078.35  5026.2 1080.00  5029.5 1076.49
  5029.7 1073.49  5033.2 1073.49  5033.5 1076.49  5051.6 1079.54  5073.1 1076.79
  5087.4 1076.71  5150.0 1078.66  5200.9 1081.86  5261.5 1084.08  5338.7 1085.00
#Mann=3,-1,0
  4516.7    0.05       0  5029.5    0.05       0  5033.5    0.05       0
Bank Sta=5029.5,5033.5
Exp/Cntr=0.3,0.1

Type RM Length L Ch R = 1,28436,421,421,421
BEGIN DESCRIPTION:
Mapping XS 29f7bdee
END DESCRIPTION:
XS GIS Cut Line= 4
      2875747.13     10250625.94      2875405.45     10250541.48
      2875140.58     10250583.70      2875064.98     10250659.30
#Sta/Elev= 30
  4643.6 1087.33  4665.7 1087.15  4686.3 1086.52  4706.9 1086.50  4727.5 1085.50
  4756.4 1085.05  4761.6 1084.25  4797.8 1083.12  4851.1 1080.42  4861.4 1080.20
  4880.7 1079.12  4885.9 1079.19  4927.3 1076.70  4968.7 1074.85  4974.7 1074.34
  4985.0 1072.74  4990.9 1072.36  4991.1 1069.36  4994.6 1069.36  4994.9 1072.36
  5025.7 1073.11  5046.0 1074.06  5066.2 1075.46  5157.3 1077.48  5238.4 1081.21
  5309.3 1082.35  5316.3 1082.83  5323.4 1082.55  5351.7 1083.25  5370.7 1083.30
#Mann=3,-1,0
  4643.6    0.05       0  4990.9    0.05       0  4994.9    0.05       0
Bank Sta=4990.9,4994.9
Exp/Cntr=0.3,0.1

Type RM Length L Ch R = 1,28015,484,484,484
BEGIN DESCRIPTION:
SANDY CREEK 55.0
END DESCRIPTION:
XS GIS Cut Line= 3
      2875505.66     10250253.11      2875188.50     10250248.00
      2875105.68     10250453.11
#Sta/Elev= 30
  4682.8 1077.81  4742.8 1075.40  4782.8 1074.16  4802.8 1074.02  4832.8 1073.37
  4862.8 1072.54  4872.8 1071.99  4892.8 1071.68  4932.8 1070.41  4972.8 1068.52
  4982.8 1067.79  4993.4 1067.53  4993.7 1064.53  4997.2 1064.53  4997.4 1067.53
  5005.5 1069.23  5050.8 1070.98  5069.6 1072.15  5075.0 1072.20  5091.8 1073.08
  5099.1 1073.81  5104.5 1073.43  5123.2 1074.11  5134.9 1073.71  5152.8 1075.22
  5176.9 1076.07  5182.3 1076.05  5199.6 1077.14  5211.8 1077.31  5221.2 1077.86
#Mann=3,-1,0
  4682.8    0.05       0  4993.4    0.03       0  4997.4    0.05       0
Bank Sta=4993.4,4997.4
Exp/Cntr=0.3,0.1

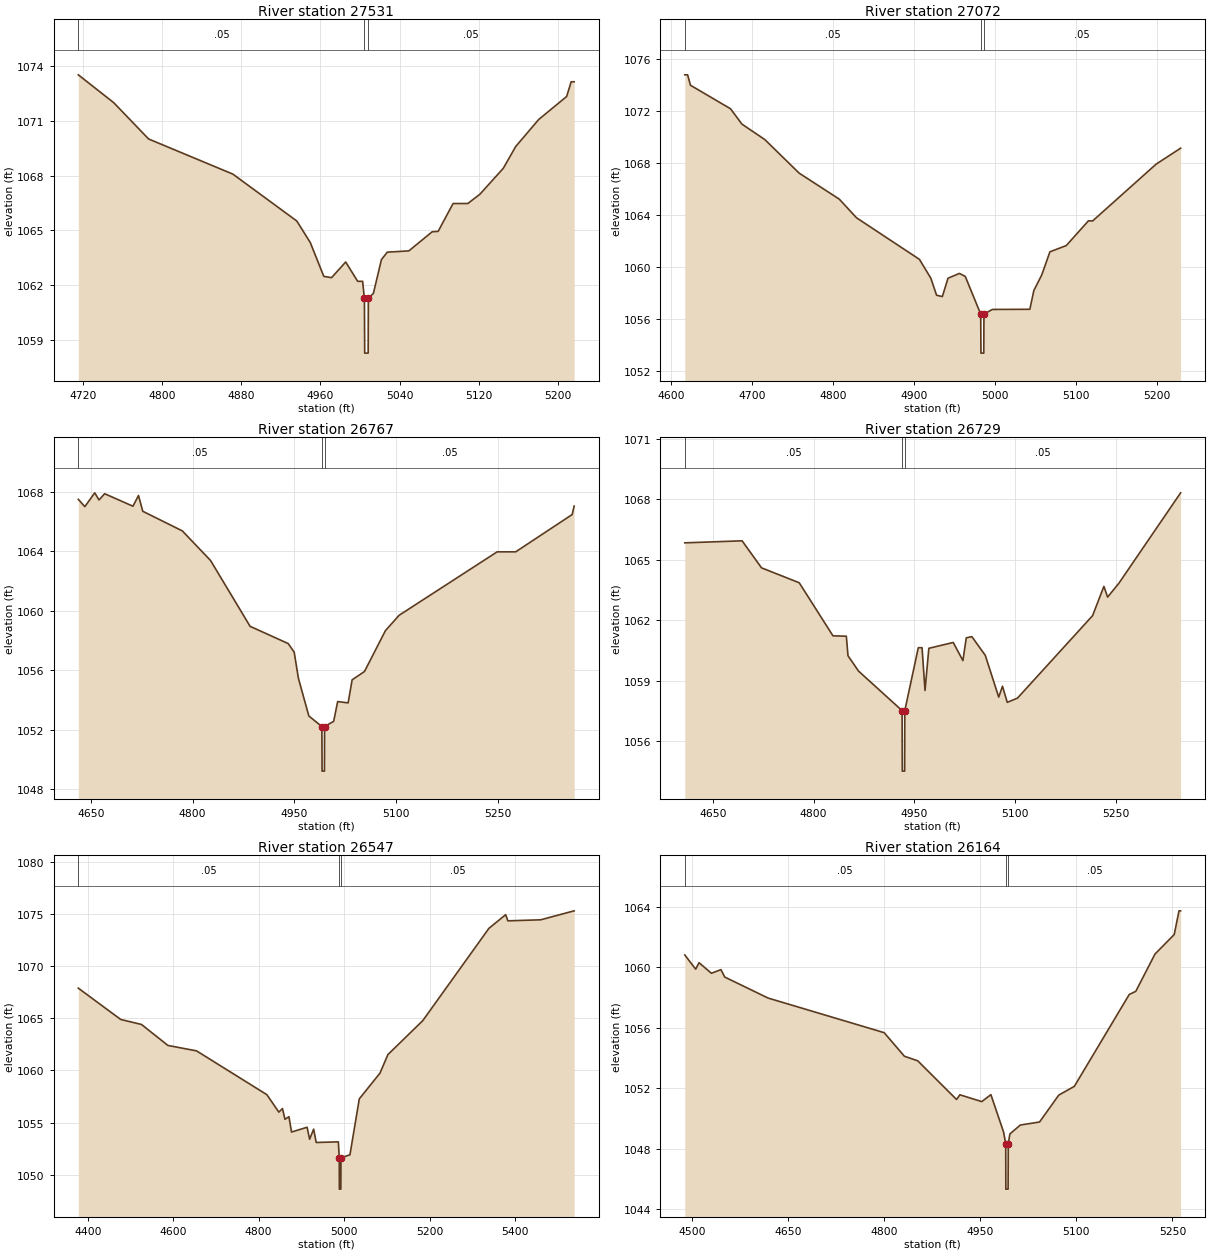
Type RM Length L Ch R = 1,27531,459,459,459
BEGIN DESCRIPTION:
SANDY CREEK 54.0
END DESCRIPTION:
XS GIS Cut Line= 3
      2875455.70     10250003.12      2875237.00     10249821.00
      2875055.66     10249703.10
#Sta/Elev= 30
  4715.4 1073.53  4751.2 1072.00  4786.4 1070.01  4871.6 1068.08  4936.1 1065.51
  4949.7 1064.33  4963.4 1062.47  4971.2 1062.40  4985.5 1063.26  4997.6 1062.20
  5002.6 1062.20  5004.4 1061.26  5004.7 1058.26  5008.2 1058.26  5008.4 1061.26
  5013.5 1061.54  5021.6 1063.39  5027.5 1063.80  5049.3 1063.87  5072.9 1064.92
  5078.9 1064.94  5094.0 1066.47  5108.9 1066.47  5121.1 1066.98  5144.7 1068.40
  5157.3 1069.60  5180.5 1071.08  5208.7 1072.34  5213.3 1073.15  5216.3 1073.15
#Mann=3,-1,0
  4715.4    0.05       0  5004.4    0.05       0  5008.4    0.05       0
Bank Sta=5004.4,5008.4
Exp/Cntr=0.3,0.1

Type RM Length L Ch R = 1,27072,305,305,305
BEGIN DESCRIPTION:
SANDY CREEK 53.0
END DESCRIPTION:
XS GIS Cut Line= 3
      2875705.66     10249753.08      2875433.25     10249484.00
      2875205.64     10249453.11
#Sta/Elev= 30
  4617.1 1074.75  4620.6 1074.75  4624.1 1073.95  4673.6 1072.14  4687.7 1070.96
  4716.0 1069.77  4758.4 1067.19  4808.0 1065.19  4829.2 1063.76  4907.0 1060.56
  4921.1 1059.11  4928.2 1057.80  4935.3 1057.70  4942.3 1059.11  4956.4 1059.48
  4963.6 1059.25  4982.7 1056.35  4983.0 1053.35  4986.5 1053.35  4986.7 1056.35
  4997.1 1056.71  5043.4 1056.72  5048.4 1058.17  5058.1 1059.36  5068.2 1061.14
  5088.4 1061.62  5115.9 1063.53  5120.9 1063.51  5199.4 1067.88  5229.7 1069.11
#Mann=3,-1,0
  4617.1    0.05       0  4982.7    0.05       0  4986.7    0.05       0
Bank Sta=4982.7,4986.7
Exp/Cntr=0.3,0.1

Type RM Length L Ch R = 1,26767,38,38,38
BEGIN DESCRIPTION:
Mapping XS 23d10475
END DESCRIPTION:
XS GIS Cut Line= 4
      2875869.96     10249512.73      2875620.41     10249324.61
      2875539.80     10249274.71      2875225.43     10249198.03
#Sta/Elev= 30
  4631.7 1067.48  4641.3 1066.99  4655.9 1067.92  4662.2 1067.44  4670.5 1067.86
  4712.2 1067.02  4720.4 1067.74  4726.7 1066.68  4785.0 1065.36  4826.6 1063.37
  4884.9 1058.94  4941.1 1057.78  4949.9 1057.20  4956.1 1055.45  4971.5 1052.91
  4990.7 1052.20  4991.0 1049.20  4994.5 1049.20  4994.7 1052.20  5008.1 1052.55
  5014.0 1053.88  5029.4 1053.79  5035.3 1055.34  5053.5 1055.90  5084.4 1058.65
  5104.5 1059.68  5249.1 1063.95  5276.4 1063.95  5359.7 1066.46  5362.6 1067.03
#Mann=3,-1,0
  4631.7    0.05       0  4990.7    0.05       0  4994.7    0.05       0
Bank Sta=4990.7,4994.7
Exp/Cntr=0.3,0.1

Type RM Length L Ch R = 1,26729,182,182,182
BEGIN DESCRIPTION:
Mapping XS 1503cd76
END DESCRIPTION:
XS GIS Cut Line= 6
      2875881.46     10249497.38      2875735.57     10249309.26
      2875628.09     10249282.39      2875585.87     10249259.35
      2875528.29     10249255.52      2875274.94     10249128.85
#Sta/Elev= 30
  4608.2 1065.84  4693.5 1065.94  4722.4 1064.60  4778.5 1063.86  4828.7 1061.23
  4848.6 1061.21  4851.1 1060.24  4866.8 1059.48  4931.6 1057.52  4931.9 1054.52
  4935.4 1054.52  4935.6 1057.52  4955.7 1060.64  4961.3 1060.64  4965.7 1058.52
  4971.4 1060.61  5007.7 1060.90  5022.1 1060.00  5027.1 1061.13  5035.4 1061.19
  5055.4 1060.26  5075.4 1058.19  5081.0 1058.73  5088.1 1057.93  5103.3 1058.14
  5215.1 1062.23  5231.9 1063.68  5237.5 1063.15  5254.3 1063.84  5346.1 1068.32
#Mann=3,-1,0
  4608.2    0.05       0  4931.6    0.05       0  4935.6    0.05       0
Bank Sta=4931.6,4935.6
Exp/Cntr=0.3,0.1

Type RM Length L Ch R = 1,26547,383,383,383
BEGIN DESCRIPTION:
Mapping XS 6309e039
END DESCRIPTION:
XS GIS Cut Line= 6
      2875916.00     10249581.84      2875892.96     10249355.32
      2875789.32     10249240.16      2875593.54     10249117.32
      2875516.77     10249071.26      2875069.15     10248975.61
#Sta/Elev= 30
  4377.7 1067.88  4476.9 1064.88  4525.6 1064.40  4587.5 1062.39  4654.5 1061.87
  4819.2 1057.67  4847.2 1056.00  4855.7 1056.34  4861.6 1055.31  4870.9 1055.56
  4876.9 1054.09  4913.4 1054.55  4919.3 1053.40  4928.7 1054.37  4934.7 1053.09
  4986.5 1053.15  4988.7 1051.62  4988.9 1048.62  4992.4 1048.62  4992.7 1051.62
  5013.7 1051.91  5035.6 1057.27  5084.1 1059.74  5102.5 1061.51  5184.3 1064.77
  5339.1 1073.61  5378.3 1074.92  5383.5 1074.33  5460.4 1074.43  5538.7 1075.29
#Mann=3,-1,0
  4377.7    0.05       0  4988.7    0.05       0  4992.7    0.05       0
Bank Sta=4988.7,4992.7
Exp/Cntr=0.3,0.1

Type RM Length L Ch R = 1,26164,480,480,480
BEGIN DESCRIPTION:
SANDY CREEK 51.0
END DESCRIPTION:
XS GIS Cut Line= 3
      2875955.67     10249353.07      2875818.25     10248861.00
      2875555.67     10248853.11
#Sta/Elev= 30
  4489.1 1060.82  4506.1 1059.88  4511.3 1060.31  4530.6 1059.61  4545.5 1059.85
  4551.4 1059.36  4619.0 1057.97  4800.2 1055.68  4831.7 1054.12  4852.5 1053.82
  4913.1 1051.26  4918.3 1051.57  4952.4 1051.12  4966.7 1051.58  4986.6 1049.09
  4989.8 1048.33  4990.0 1045.33  4993.5 1045.33  4993.8 1048.33  4996.3 1048.98
  5012.6 1049.57  5042.6 1049.77  5072.6 1051.55  5096.9 1052.13  5182.6 1058.21
  5192.7 1058.41  5222.7 1060.88  5252.7 1062.17  5260.2 1063.74  5262.7 1063.74
#Mann=3,-1,0
  4489.1    0.05       0  4989.8    0.05       0  4993.8    0.05       0
Bank Sta=4989.8,4993.8
Exp/Cntr=0.3,0.1

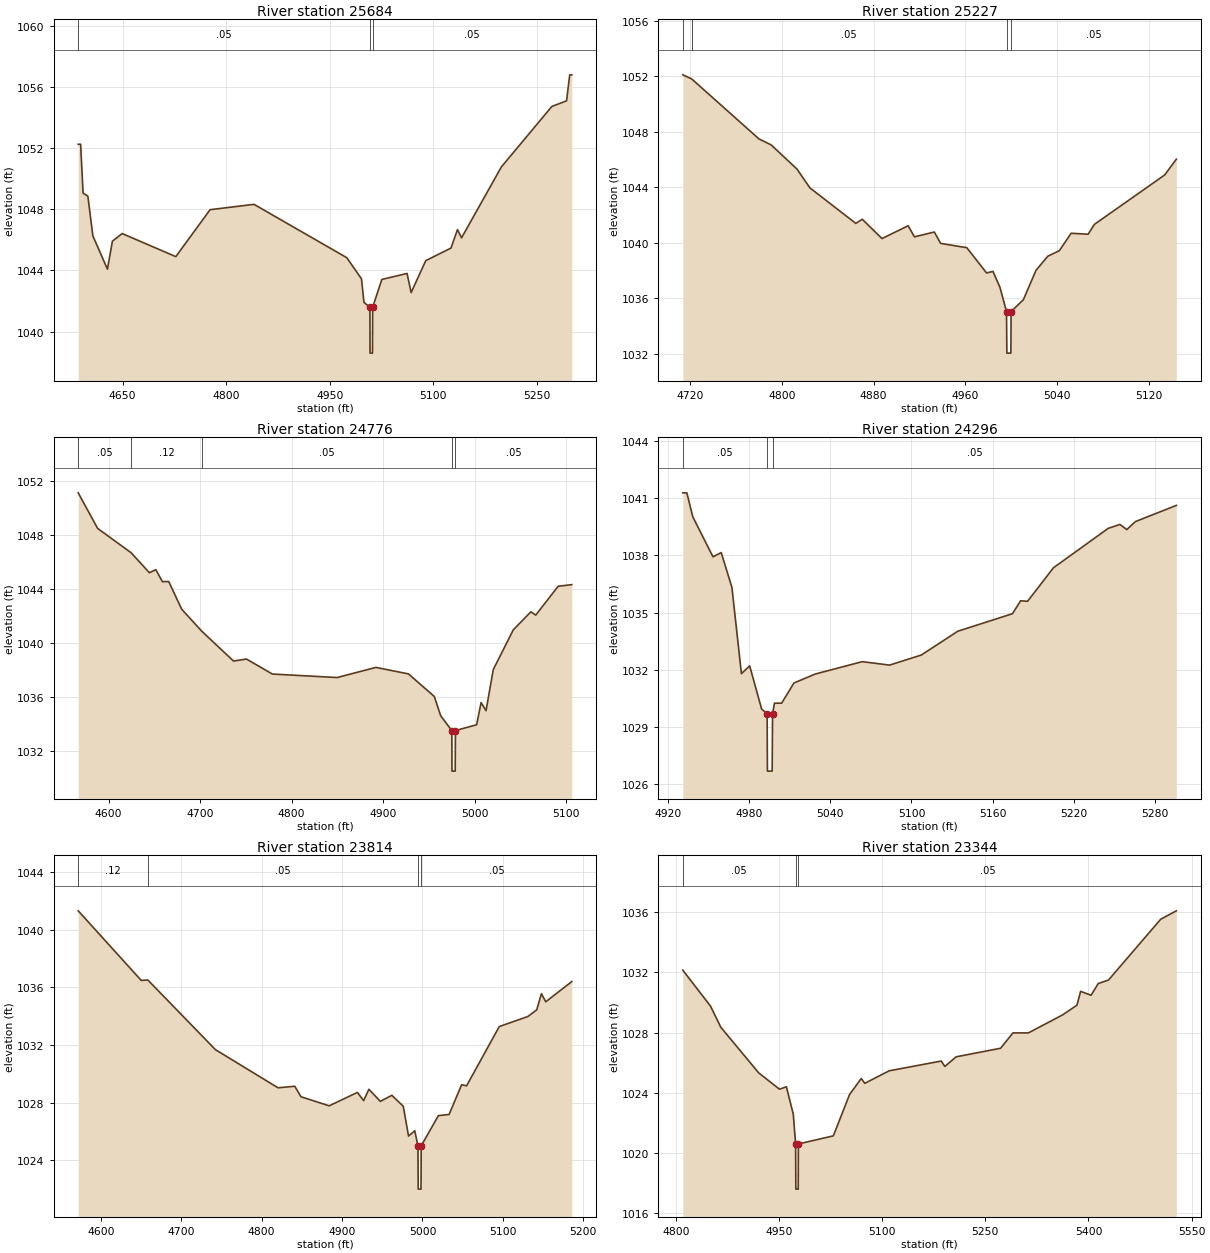
Type RM Length L Ch R = 1,25684,457,457,457
BEGIN DESCRIPTION:
SANDY CREEK 50.0
END DESCRIPTION:
XS GIS Cut Line= 3
      2876305.66     10248753.08      2876010.00     10248463.00
      2875755.69     10248303.11
#Sta/Elev= 30
  4585.8 1052.25  4589.3 1052.25  4592.8 1049.06  4599.8 1048.85  4607.0 1046.26
  4628.1 1044.08  4635.3 1045.91  4649.4 1046.41  4727.1 1044.90  4776.7 1047.97
  4840.3 1048.32  4974.7 1044.83  4995.9 1043.45  4999.5 1041.91  5008.1 1041.59
  5008.3 1038.59  5011.8 1038.59  5012.1 1041.59  5025.4 1043.41  5061.9 1043.80
  5067.8 1042.55  5089.0 1044.64  5125.5 1045.46  5134.9 1046.67  5140.8 1046.13
  5198.5 1050.77  5271.5 1054.72  5292.8 1055.09  5297.4 1056.79  5300.4 1056.79
#Mann=3,-1,0
  4585.8    0.05       0  5008.1    0.05       0  5012.1    0.05       0
Bank Sta=5008.1,5012.1
Exp/Cntr=0.3,0.1

Type RM Length L Ch R = 1,25227,451,451,451
BEGIN DESCRIPTION:
SANDY CREEK 49.0
END DESCRIPTION:
XS GIS Cut Line= 3
      2876405.70     10248203.12      2876146.75     10248081.00
      2876005.68     10248053.11
#Sta/Elev= 30
  4713.7 1052.12  4721.4 1051.83  4780.1 1047.50  4790.7 1047.07  4813.2 1045.33
  4824.5 1043.97  4864.5 1041.41  4870.1 1041.71  4887.3 1040.32  4910.1 1041.24
  4915.6 1040.44  4932.9 1040.79  4938.4 1039.97  4961.2 1039.66  4978.4 1037.84
  4984.0 1037.95  4990.1 1036.80  4995.8 1035.06  4996.1 1032.06  4999.6 1032.06
  4999.8 1035.06  5010.5 1035.91  5021.5 1038.03  5031.7 1039.04  5041.9 1039.45
  5052.1 1040.70  5066.9 1040.63  5072.4 1041.34  5133.6 1044.90  5143.8 1046.04
#Mann=4,-1,0
  4713.7    0.12       0  4721.4    0.05       0  4995.8    0.05       0
  4999.8    0.05       0
Bank Sta=4995.8,4999.8
Exp/Cntr=0.3,0.1

Type RM Length L Ch R = 1,24776,480,480,480
BEGIN DESCRIPTION:
SANDY CREEK 48.0
END DESCRIPTION:
XS GIS Cut Line= 3
      2876505.69     10248053.11      2876194.25     10247752.00
      2876155.70     10247653.15
#Sta/Elev= 30
  4566.8 1051.10  4588.0 1048.47  4624.6 1046.67  4644.6 1045.19  4651.6 1045.42
  4658.8 1044.53  4665.7 1044.54  4679.9 1042.49  4701.9 1040.86  4736.5 1038.66
  4750.6 1038.81  4778.9 1037.70  4849.6 1037.44  4892.1 1038.19  4927.6 1037.71
  4955.9 1036.04  4962.8 1034.62  4975.0 1033.52  4975.2 1030.52  4978.7 1030.52
  4979.0 1033.52  5002.1 1033.95  5007.0 1035.59  5012.4 1034.99  5020.3 1038.03
  5042.2 1040.97  5061.4 1042.30  5066.7 1042.06  5091.2 1044.19  5106.1 1044.31
#Mann=5,-1,0
  4566.8    0.05       0  4624.6    0.12       0  4701.9    0.05       0
  4975.0    0.05       0  4979.0    0.05       0
Bank Sta=4975,4979
Exp/Cntr=0.3,0.1

Type RM Length L Ch R = 1,24296,482,482,482
BEGIN DESCRIPTION:
SANDY CREEK 47.0
END DESCRIPTION:
XS GIS Cut Line= 3
      2876655.64     10247553.14      2876598.75     10247592.00
      2876305.72     10247553.12
#Sta/Elev= 30
  4931.1 1041.29  4934.1 1041.29  4938.5 1040.03  4953.4 1037.93  4959.5 1038.15
  4967.4 1036.32  4974.4 1031.79  4980.5 1032.20  4989.3 1029.94  4993.4 1029.67
  4993.6 1026.67  4997.1 1026.67  4997.4 1029.67  4998.8 1030.24  5004.1 1030.24
  5013.2 1031.30  5028.9 1031.77  5063.6 1032.42  5083.8 1032.24  5107.3 1032.77
  5134.2 1034.02  5174.6 1034.94  5180.6 1035.62  5185.7 1035.59  5204.8 1037.35
  5245.2 1039.42  5253.9 1039.63  5259.0 1039.36  5265.4 1039.78  5295.6 1040.63
#Mann=3,-1,0
  4931.1    0.05       0  4993.4    0.05       0  4997.4    0.05       0
Bank Sta=4993.4,4997.4
Exp/Cntr=0.3,0.1

Type RM Length L Ch R = 1,23814,470,470,470
BEGIN DESCRIPTION:
SANDY CREEK 46.0
END DESCRIPTION:
XS GIS Cut Line= 3
      2876805.68     10247453.11      2876526.00     10247129.00
      2876355.72     10247203.09
#Sta/Elev= 30
  4571.9 1041.30  4650.3 1036.47  4658.5 1036.50  4742.5 1031.67  4820.4 1029.02
  4841.2 1029.13  4848.9 1028.40  4884.0 1027.77  4919.1 1028.70  4926.8 1028.13
  4933.4 1028.92  4947.6 1028.08  4961.9 1028.50  4976.1 1027.74  4982.7 1025.67
  4990.4 1026.04  4994.4 1024.99  4994.7 1021.99  4998.2 1021.99  4998.4 1024.99
  5019.8 1027.09  5033.1 1027.17  5048.7 1029.23  5054.9 1029.16  5095.5 1033.27
  5131.2 1033.97  5142.1 1034.43  5147.9 1035.55  5153.3 1034.99  5185.7 1036.39
#Mann=4,-1,0
  4571.9    0.12       0  4658.5    0.05       0  4994.4    0.05       0
  4998.4    0.05       0
Bank Sta=4994.4,4998.4
Exp/Cntr=0.3,0.1

Type RM Length L Ch R = 1,23344,482,482,482
BEGIN DESCRIPTION:
SANDY CREEK 45.0
END DESCRIPTION:
XS GIS Cut Line= 3
      2877105.73     10246953.12      2876916.50     10246936.00
      2876405.70     10246803.12
#Sta/Elev= 30
  4810.0 1032.15  4850.2 1029.77  4865.4 1028.35  4920.5 1025.32  4950.6 1024.24
  4960.7 1024.40  4970.7 1022.58  4974.1 1020.60  4974.4 1017.60  4977.9 1017.60
  4978.1 1020.60  5029.0 1021.14  5052.5 1023.88  5069.5 1024.95  5074.7 1024.63
  5110.1 1025.46  5185.9 1026.11  5191.1 1025.75  5207.5 1026.39  5272.2 1026.96
  5290.2 1027.98  5312.7 1027.98  5362.5 1029.18  5383.2 1029.82  5388.6 1030.74
  5403.8 1030.48  5414.2 1031.26  5429.1 1031.49  5505.0 1035.53  5527.8 1036.09
#Mann=3,-1,0
  4810.0    0.05       0  4974.1    0.05       0  4978.1    0.05       0
Bank Sta=4974.1,4978.1
Exp/Cntr=0.3,0.1

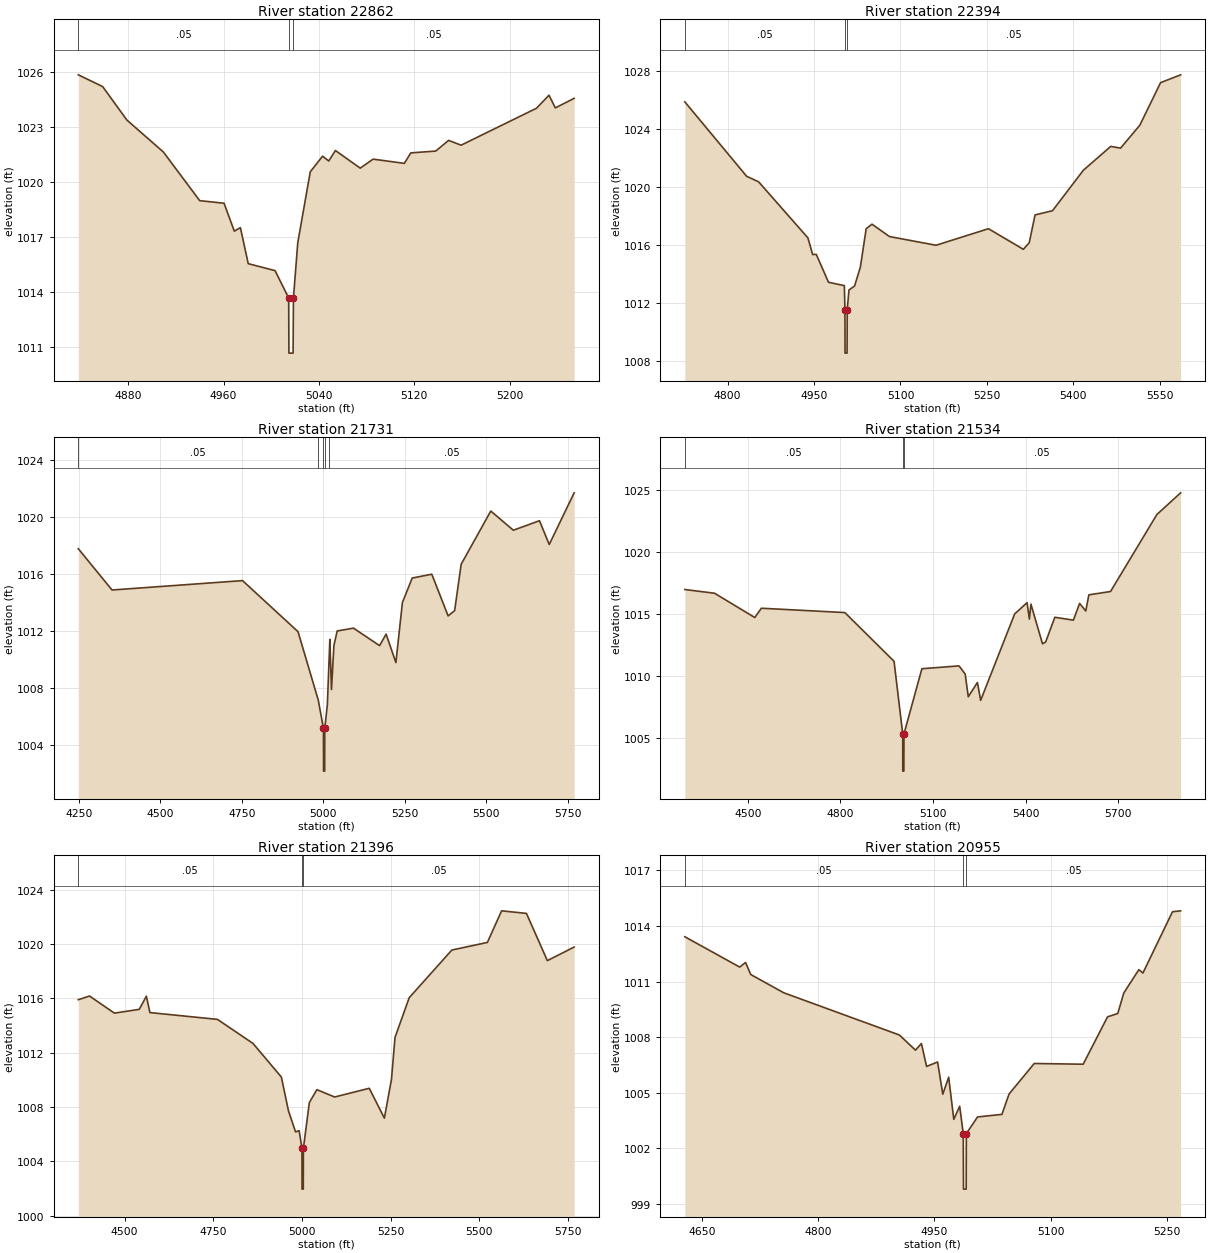
Type RM Length L Ch R = 1,22862,468,468,468
BEGIN DESCRIPTION:
SANDY CREEK 44.0
END DESCRIPTION:
XS GIS Cut Line= 3
      2877155.72     10246503.12      2876996.75     10246473.00
      2876755.71     10246553.10
#Sta/Elev= 30
  4838.2 1025.83  4858.6 1025.19  4878.9 1023.37  4909.5 1021.63  4940.0 1018.98
  4960.4 1018.84  4969.0 1017.32  4974.1 1017.51  4980.7 1015.55  5003.2 1015.17
  5014.6 1013.68  5014.8 1010.68  5018.3 1010.68  5018.6 1013.68  5022.2 1016.68
  5032.7 1020.55  5043.0 1021.40  5048.2 1021.14  5053.8 1021.71  5074.6 1020.75
  5085.4 1021.24  5111.6 1021.01  5117.0 1021.58  5137.9 1021.68  5148.7 1022.26
  5159.2 1022.00  5222.4 1024.01  5232.9 1024.72  5238.2 1024.03  5254.0 1024.55
#Mann=3,-1,0
  4838.2    0.05       0  5014.6    0.05       0  5018.6    0.05       0
Bank Sta=5014.6,5018.6
Exp/Cntr=0.3,0.1

Type RM Length L Ch R = 1,22394,663,663,663
BEGIN DESCRIPTION:
SANDY CREEK 43.0
END DESCRIPTION:
XS GIS Cut Line= 3
      2877255.67     10246203.10      2877035.75     10246039.00
      2876455.67     10245953.11
#Sta/Elev= 30
  4725.6 1025.86  4833.0 1020.73  4853.8 1020.35  4939.3 1016.49  4947.6 1015.34
  4953.9 1015.35  4975.1 1013.43  5002.6 1013.20  5003.6 1011.55  5003.8 1008.55
  5007.3 1008.55  5007.6 1011.55  5010.6 1012.90  5020.3 1013.17  5030.4 1014.47
  5040.5 1017.12  5050.6 1017.43  5080.9 1016.58  5161.8 1015.98  5252.8 1017.12
  5313.4 1015.70  5323.6 1016.16  5333.7 1018.07  5364.0 1018.36  5417.6 1021.15
  5465.1 1022.79  5482.1 1022.67  5515.6 1024.25  5551.6 1027.18  5586.4 1027.72
#Mann=3,-1,0
  4725.6    0.05       0  5003.6    0.05       0  5007.6    0.05       0
Bank Sta=5003.6,5007.6
Exp/Cntr=0.3,0.1

Type RM Length L Ch R = 1,21731,197,197,197
BEGIN DESCRIPTION:
Mapping XS 531fbbfe
END DESCRIPTION:
XS GIS Cut Line= 2
      2877638.99     10245416.33      2876119.37     10245478.78
#Sta/Elev= 30
  4248.2 1017.78  4351.6 1014.88  4751.9 1015.54  4922.1 1011.95  4984.2 1007.14
  5000.1 1005.15  5000.4 1002.15  5003.9 1002.15  5004.1 1005.15  5012.1 1006.83
  5017.4 1010.02  5019.7 1011.41  5024.7 1007.89  5032.2 1010.98  5042.2 1012.00
  5092.2 1012.20  5172.3 1010.97  5192.3 1011.78  5222.3 1009.78  5242.3 1014.00
  5272.4 1015.72  5332.4 1015.99  5382.5 1013.06  5402.5 1013.43  5422.5 1016.69
  5513.4 1020.43  5582.6 1019.08  5662.7 1019.75  5692.7 1018.08  5769.1 1021.71
#Mann=5,-1,0
  4248.2    0.05       0  4984.2    0.12       0  5000.1    0.07       0
  5004.1    0.12       0  5017.4    0.05       0
Bank Sta=5000.1,5004.1
Exp/Cntr=0.3,0.1

Type RM Length L Ch R = 1,21534,138,138,138
BEGIN DESCRIPTION:
Mapping XS fe558d50
END DESCRIPTION:
XS GIS Cut Line= 3
      2877681.82     10245336.22      2876906.37     10245278.63
      2876078.95     10245228.83
#Sta/Elev= 30
  4296.0 1017.00  4392.4 1016.70  4522.8 1014.74  4544.1 1015.49  4814.6 1015.14
  4974.0 1011.21  5002.1 1005.35  5002.3 1002.35  5005.8 1002.35  5006.1 1005.35
  5064.2 1010.61  5184.5 1010.84  5204.5 1010.18  5214.5 1008.35  5244.1 1009.50
  5254.6 1008.06  5364.8 1015.03  5404.9 1015.94  5412.5 1014.62  5417.5 1015.82
  5455.0 1012.62  5465.0 1012.76  5495.0 1014.76  5555.1 1014.53  5575.2 1015.88
  5595.2 1015.27  5605.2 1016.57  5675.4 1016.84  5825.6 1023.05  5902.5 1024.80
#Mann=3,-1,0
  4296.0    0.05       0  5002.1    0.03       0  5006.1    0.05       0
Bank Sta=5002.1,5006.1
Exp/Cntr=0.3,0.1

Type RM Length L Ch R = 1,21396,441,441,441
BEGIN DESCRIPTION:
Mapping XS 8c5d00aa
END DESCRIPTION:
XS GIS Cut Line= 2
      2877597.24     10245187.16      2876201.43     10245103.83
#Sta/Elev= 30
  4369.5 1015.91  4401.1 1016.18  4471.2 1014.92  4541.4 1015.20  4561.4 1016.17
  4571.4 1014.96  4761.8 1014.46  4862.0 1012.69  4942.1 1010.21  4962.1 1007.72
  4982.1 1006.17  4992.2 1006.26  5000.2 1004.95  5000.4 1001.95  5003.9 1001.95
  5004.2 1004.95  5021.0 1008.33  5042.3 1009.28  5092.3 1008.74  5190.0 1009.38
  5232.6 1007.18  5252.6 1010.04  5262.6 1013.13  5302.7 1016.06  5422.9 1019.57
  5523.1 1020.13  5563.2 1022.46  5633.3 1022.27  5692.2 1018.79  5767.8 1019.79
#Mann=3,-1,0
  4369.5    0.05       0  5000.2    0.05       0  5004.2    0.05       0
Bank Sta=5000.2,5004.2
Exp/Cntr=0.3,0.1

Type RM Length L Ch R = 1,20955,449,449,449
BEGIN DESCRIPTION:
SANDY CREEK 40.0
END DESCRIPTION:
XS GIS Cut Line= 3
      2877255.71     10245003.14      2877011.25     10244723.00
      2876755.71     10244803.10
#Sta/Elev= 30
  4628.2 1013.42  4699.0 1011.78  4706.6 1012.03  4713.2 1011.38  4755.9 1010.39
  4905.0 1008.11  4925.8 1007.29  4933.4 1007.65  4940.1 1006.41  4954.3 1006.65
  4961.0 1004.91  4968.6 1005.83  4975.2 1003.55  4982.8 1004.26  4987.4 1002.78
  4987.7  999.78  4991.2  999.78  4991.4 1002.78  5005.8 1003.68  5037.3 1003.82
  5046.5 1004.92  5079.0 1006.57  5142.1 1006.53  5173.5 1009.09  5186.7 1009.27
  5194.5 1010.38  5213.9 1011.64  5219.2 1011.46  5257.3 1014.77  5267.8 1014.82
#Mann=3,-1,0
  4628.2    0.05       0  4987.4    0.05       0  4991.4    0.05       0
Bank Sta=4987.4,4991.4
Exp/Cntr=0.3,0.1

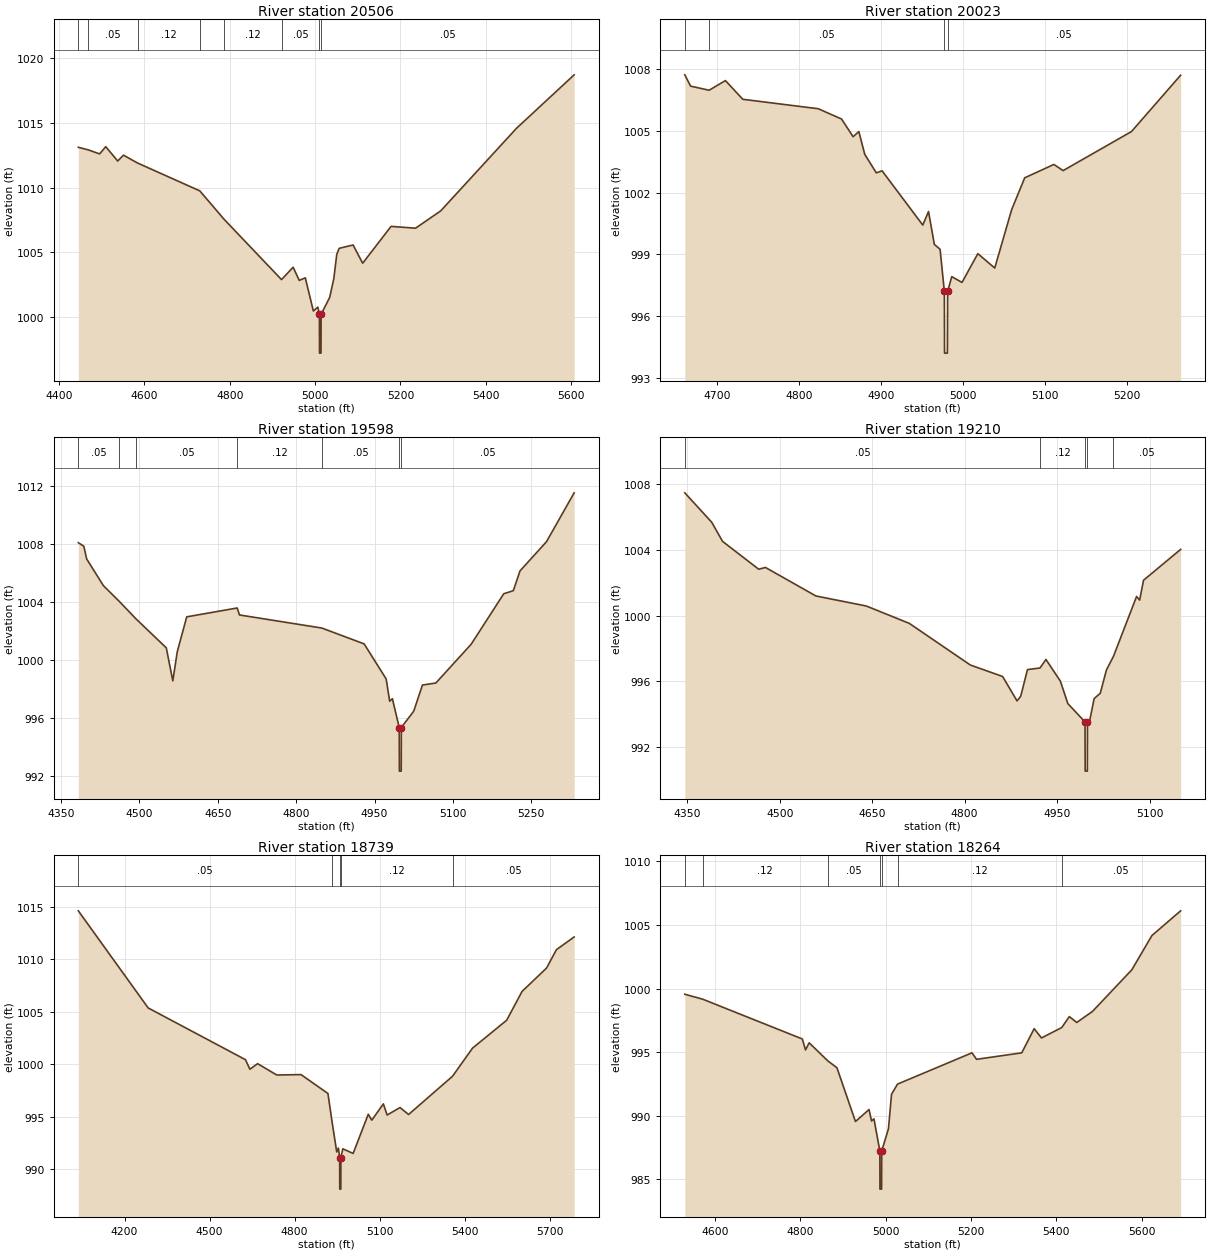
Type RM Length L Ch R = 1,20506,483,483,483
BEGIN DESCRIPTION:
SANDY CREEK 39.0
END DESCRIPTION:
XS GIS Cut Line= 3
      2877455.67     10244803.09      2877094.75     10244382.00
      2876555.72     10244103.13
#Sta/Elev= 30
  4445.4 1013.12  4468.7 1012.92  4495.3 1012.61  4509.6 1013.17  4537.6 1012.06
  4551.3 1012.51  4584.4 1011.90  4729.9 1009.75  4787.1 1007.54  4921.4 1002.88
  4948.6 1003.84  4962.9 1002.82  4977.1 1003.02  4996.0 1000.45  5006.5 1000.75
  5010.1 1000.19  5010.4  997.19  5013.9  997.19  5014.1 1000.19  5034.3 1001.51
  5044.0 1002.98  5050.8 1004.83  5056.4 1005.30  5089.0 1005.56  5111.5 1004.15
  5178.0 1007.00  5235.4 1006.86  5294.3 1008.20  5471.8 1014.59  5606.9 1018.73
#Mann=8,-1,0
  4445.4    0.12       0  4468.7    0.05       0  4584.4    0.12       0
  4729.9    0.05       0  4787.1    0.12       0  4921.4    0.05       0
  5010.1    0.03       0  5014.1    0.05       0
Bank Sta=5010.1,5014.1
Exp/Cntr=0.3,0.1

Type RM Length L Ch R = 1,20023,425,425,425
BEGIN DESCRIPTION:
SANDY CREEK 38.0
END DESCRIPTION:
XS GIS Cut Line= 3
      2877405.69     10244253.12      2877163.00     10244016.00
      2876905.67     10243953.11
#Sta/Elev= 30
  4660.7 1007.73  4667.8 1007.18  4690.3 1006.98  4710.2 1007.45  4731.4 1006.54
  4823.4 1006.08  4851.7 1005.58  4865.8 1004.72  4872.8 1004.97  4880.0 1003.86
  4894.1 1002.96  4901.1 1003.06  4950.7 1000.42  4957.7 1001.08  4964.8  999.48
  4971.8  999.24  4977.0  997.19  4977.2  994.19  4980.7  994.19  4981.0  997.19
  4986.0  997.91  4998.5  997.63  5017.8  999.03  5038.4  998.33  5059.0 1001.17
  5074.9 1002.72  5110.5 1003.37  5121.7 1003.07  5205.0 1004.97  5264.9 1007.71
#Mann=4,-1,0
  4660.7    0.12       0  4690.3    0.05       0  4977.0    0.03       0
  4981.0    0.05       0
Bank Sta=4977,4981
Exp/Cntr=0.3,0.1

Type RM Length L Ch R = 1,19598,388,388,388
BEGIN DESCRIPTION:
SANDY CREEK 37.0
END DESCRIPTION:
XS GIS Cut Line= 3
      2877805.69     10243803.12      2877219.25     10243612.00
      2876905.72     10243503.12
#Sta/Elev= 30
  4383.2 1008.07  4393.7 1007.83  4399.2 1006.95  4431.1 1005.12  4461.4 1004.04
  4493.6 1002.83  4551.5 1000.84  4564.0  998.57  4572.5 1000.57  4590.6 1002.97
  4687.1 1003.58  4691.6 1003.10  4849.2 1002.20  4930.1 1001.11  4972.2  998.70
  4978.9  997.17  4984.1  997.34  4997.2  995.36  4997.5  992.36  5001.0  992.36
  5001.2  995.36  5024.9  996.48  5041.6  998.28  5067.3  998.42  5134.9 1001.09
  5197.2 1004.56  5215.5 1004.77  5228.3 1006.13  5279.0 1008.14  5331.9 1011.50
#Mann=7,-1,0
  4383.2    0.05       0  4461.4    0.12       0  4493.6    0.05       0
  4687.1    0.12       0  4849.2    0.05       0  4997.2    0.03       0
  5001.2    0.05       0
Bank Sta=4997.2,5001.2
Exp/Cntr=0.3,0.1

Type RM Length L Ch R = 1,19210,471,471,471
BEGIN DESCRIPTION:
SANDY CREEK 36.0
END DESCRIPTION:
XS GIS Cut Line= 3
      2877855.69     10243503.11      2877255.75     10243242.00
      2877105.66     10243253.11
#Sta/Elev= 30
  4345.7 1007.49  4389.3 1005.70  4407.0 1004.53  4465.7 1002.83  4476.6 1002.94
  4558.5 1001.20  4640.2 1000.59  4710.1  999.53  4809.2  996.99  4861.6  996.29
  4885.0  994.80  4891.0  995.09  4901.9  996.71  4922.3  996.81  4931.9  997.33
  4955.3  996.01  4967.4  994.64  4995.3  993.52  4995.6  990.52  4999.1  990.52
  4999.3  993.52  5002.5  993.52  5010.1  994.94  5020.1  995.27  5030.1  996.69
  5041.5  997.52  5079.0 1001.17  5084.0 1000.95  5090.3 1002.16  5150.5 1004.04
#Mann=5,-1,0
  4345.7    0.05       0  4922.3    0.12       0  4995.3    0.07       0
  4999.3    0.12       0  5041.5    0.05       0
Bank Sta=4995.3,4999.3
Exp/Cntr=0.3,0.1

Type RM Length L Ch R = 1,18739,475,475,475
BEGIN DESCRIPTION:
SANDY CREEK 35.0
END DESCRIPTION:
XS GIS Cut Line= 3
      2878305.69     10243353.12      2877482.25     10242854.00
      2876755.71     10243153.10
#Sta/Elev= 30
  4037.1 1014.61  4283.4 1005.36  4626.6 1000.43  4642.1  999.52  4669.3 1000.05
  4737.1  998.97  4822.4  999.01  4917.4  997.21  4931.4  994.61  4948.4  991.64
  4954.3  992.01  4958.8  991.10  4959.1  988.10  4962.8  988.10  4963.1  991.10
  4969.8  991.94  5006.2  991.50  5059.6  995.23  5072.0  994.67  5112.9  996.22
  5126.1  995.16  5171.6  995.87  5201.8  995.21  5356.7  998.85  5427.3 1001.53
  5547.8 1004.19  5601.9 1006.93  5688.4 1009.16  5723.2 1010.91  5785.7 1012.12
#Mann=5,-1,0
  4037.1    0.05       0  4931.4    0.12       0  4958.8    0.07       0
  4963.1    0.12       0  5356.7    0.05       0
Bank Sta=4958.8,4963.1
Exp/Cntr=0.3,0.1

Type RM Length L Ch R = 1,18264,494,494,494
BEGIN DESCRIPTION:
SANDY CREEK 34.0
END DESCRIPTION:
XS GIS Cut Line= 3
      2877852.71     10242611.71      2877441.75     10242382.00
      2876805.72     10242653.10
#Sta/Elev= 30
  4529.2  999.55  4571.1  999.16  4804.7  996.03  4812.2  995.17  4820.7  995.73
  4864.7  994.30  4885.8  993.77  4929.2  989.54  4961.1  990.48  4966.9  989.58
  4972.6  989.75  4986.4  987.22  4986.7  984.22  4990.5  984.22  4990.8  987.22
  5006.6  988.97  5013.8  991.68  5027.8  992.48  5202.3  994.94  5213.1  994.43
  5319.0  994.94  5348.1  996.84  5365.3  996.11  5412.8  996.93  5430.5  997.79
  5448.0  997.33  5484.9  998.20  5577.0 1001.47  5624.2 1004.17  5691.4 1006.11
#Mann=7,-1,0
  4529.2    0.05       0  4571.1    0.12       0  4864.7    0.05       0
  4986.4    0.05       0  4990.8    0.05       0  5027.8    0.12       0
  5412.8    0.05       0
Bank Sta=4986.4,4990.8
Exp/Cntr=0.3,0.1