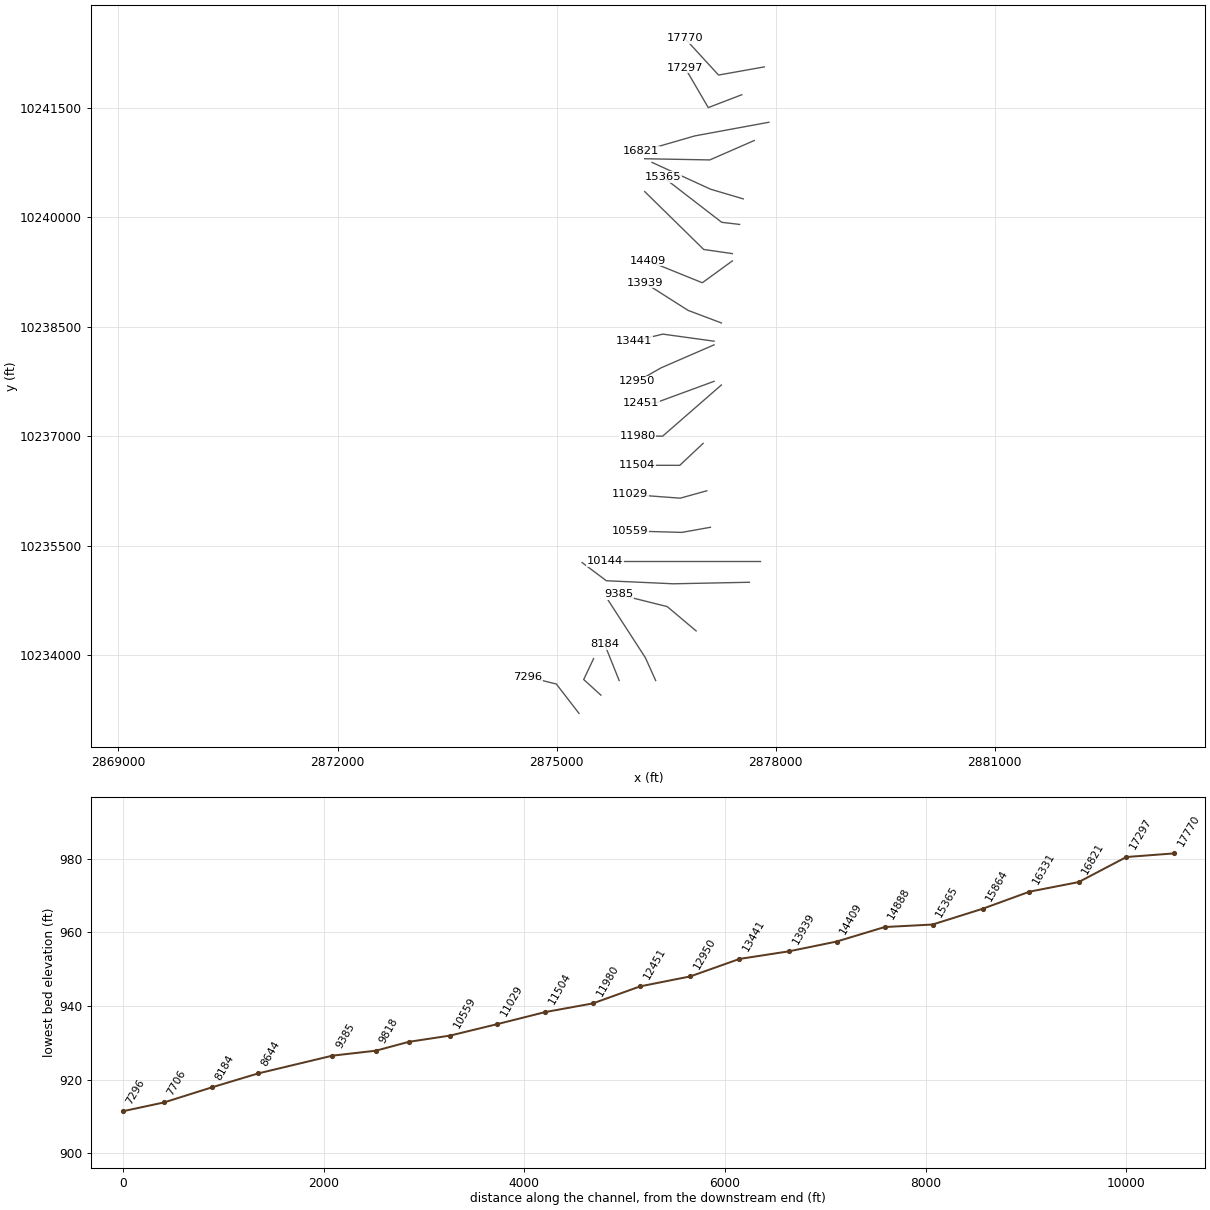
HEC-RAS study SANDY CREEK.prj: SANDY CREEK Base Level Engineering

--- SANDY CREEK.g01 (geometry) --- (continued)

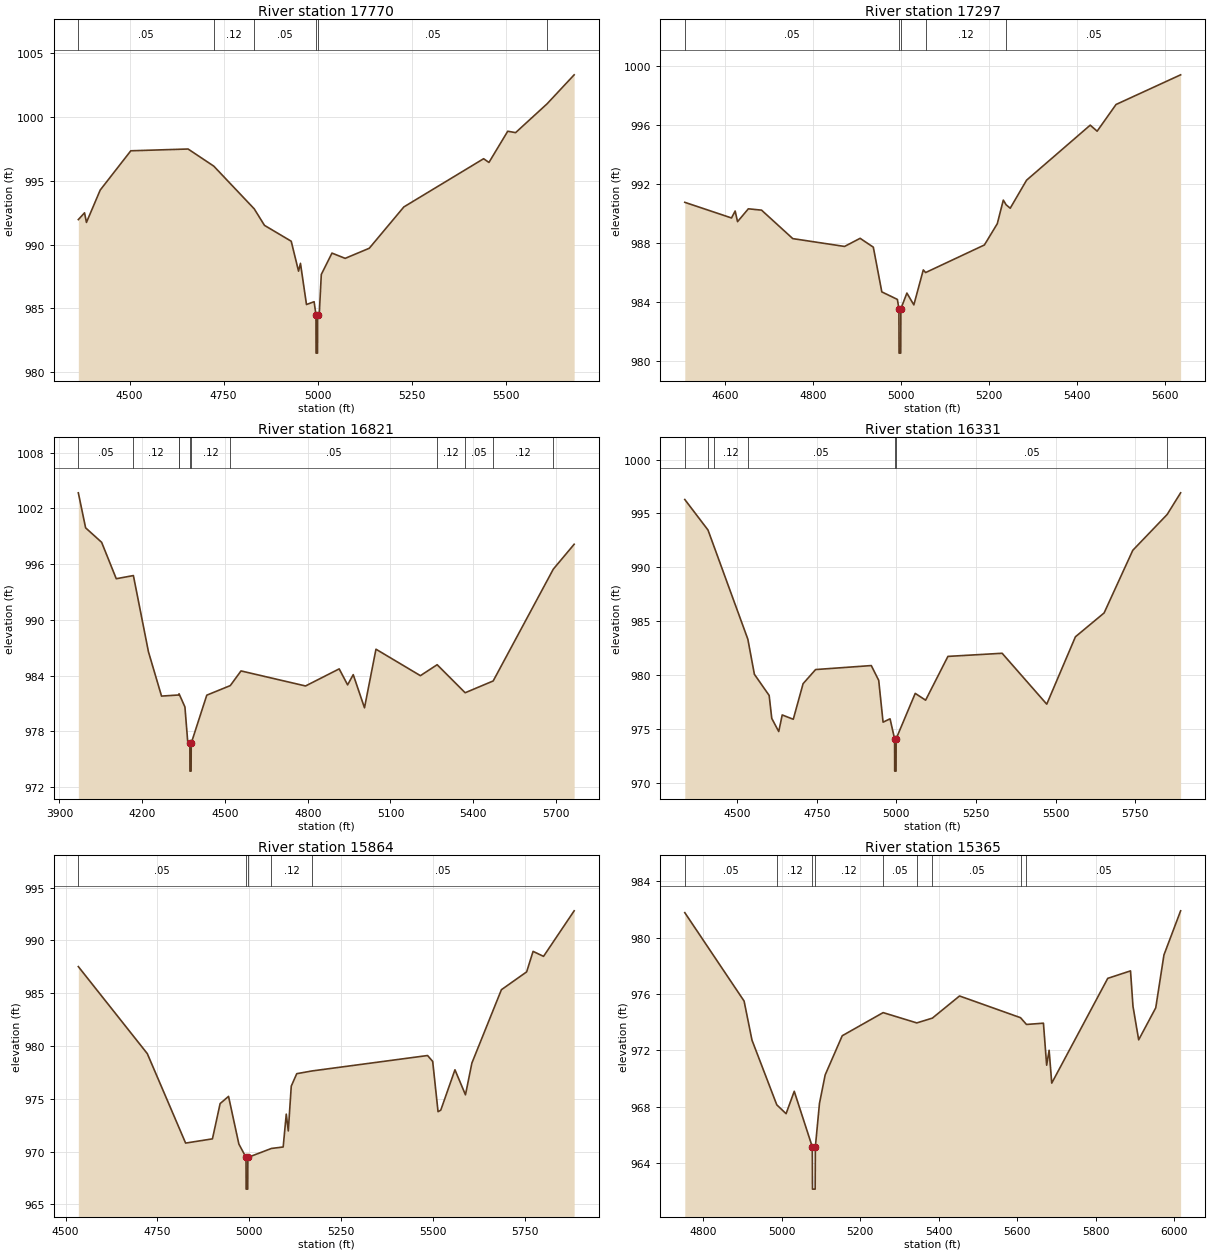
Type RM Length L Ch R = 1,17770,473,473,473
BEGIN DESCRIPTION:
SANDY CREEK 33.0
END DESCRIPTION:
XS GIS Cut Line= 3
      2877842.96     10242061.71      2877216.75     10241950.00
      2876755.70     10242453.09
#Sta/Elev= 30
  4363.9  991.95  4380.4  992.48  4385.5  991.73  4422.1  994.26  4503.4  997.33
  4655.7  997.47  4724.1  996.13  4831.7  992.79  4858.9  991.50  4930.0  990.26
  4949.5  987.92  4954.6  988.53  4970.6  985.31  4990.9  985.53  4995.8  984.51
  4996.1  981.51  4999.9  981.51  5000.2  984.51  5004.5  984.51  5010.0  987.66
  5038.4  989.33  5073.5  988.92  5137.6  989.71  5229.5  992.94  5441.6  996.71
  5455.8  996.42  5505.8  998.86  5526.7  998.75  5610.3 1001.00  5682.4 1003.27
#Mann=6,-1,0
  4363.9    0.05       0  4724.1    0.12       0  4831.7    0.05       0
  4995.8    0.03       0  5000.2    0.05       0  5610.3    0.12       0
Bank Sta=4995.8,5000.2
Exp/Cntr=0.3,0.1

Type RM Length L Ch R = 1,17297,476,476,476
BEGIN DESCRIPTION:
SANDY CREEK 32.0
END DESCRIPTION:
XS GIS Cut Line= 3
      2877534.82     10241680.24      2877076.00     10241504.00
      2876755.69     10242053.10
#Sta/Elev= 30
  4508.5  990.75  4614.7  989.69  4623.0  990.16  4628.4  989.44  4653.0  990.31
  4683.0  990.22  4754.0  988.29  4871.7  987.76  4907.1  988.31  4937.1  987.71
  4956.4  984.68  4991.8  984.17  4995.3  983.53  4995.6  980.53  4999.4  980.53
  4999.7  983.53  5013.4  984.60  5029.2  983.80  5050.7  986.17  5056.0  985.99
  5189.6  987.86  5218.9  989.30  5232.6  990.90  5239.1  990.58  5248.3  990.35
  5285.5  992.25  5430.2  995.98  5445.9  995.57  5488.9  997.38  5635.7  999.39
#Mann=5,-1,0
  4508.5    0.05       0  4995.3    0.05       0  4999.7    0.05       0
  5056.0    0.12       0  5239.1    0.05       0
Bank Sta=4995.3,4999.7
Exp/Cntr=0.3,0.1

Type RM Length L Ch R = 1,16821,490,490,490
BEGIN DESCRIPTION:
SANDY CREEK 31.0
END DESCRIPTION:
XS GIS Cut Line= 3
      2877905.64     10241303.10      2876891.25     10241116.00
      2876155.64     10240903.10
#Sta/Elev= 30
  3968.5 1003.68  3994.9  999.91  4053.0  998.35  4106.0  994.43  4168.1  994.77
  4222.7  986.56  4270.1  981.79  4332.3  981.91  4333.6  982.04  4354.9  980.62
  4365.0  976.89  4372.8  976.71  4373.1  973.71  4377.3  973.71  4377.7  976.71
  4434.1  981.89  4519.3  982.92  4558.2  984.50  4792.1  982.88  4914.1  984.72
  4944.6  983.00  4965.0  984.10  5005.8  980.53  5047.4  986.84  5208.5  983.99
  5269.2  985.17  5370.7  982.15  5472.3  983.42  5690.2  995.46  5765.8  998.14
#Mann=11,-1,0
  3968.5    0.05       0  4168.1    0.12       0  4332.3    0.05       0
  4333.6    0.12       0  4372.8    0.05       0  4377.7    0.12       0
  4519.3    0.05       0  5269.2    0.12       0  5370.7    0.05       0
  5472.3    0.12       0  5690.2    0.05       0
Bank Sta=4372.8,4377.7
Exp/Cntr=0.3,0.1

Type RM Length L Ch R = 1,16331,467,467,467
BEGIN DESCRIPTION:
SANDY CREEK 30.0
END DESCRIPTION:
XS GIS Cut Line= 3
      2877705.73     10241053.13      2877097.50     10240787.00
      2876205.65     10240803.11
#Sta/Elev= 30
  4336.1  996.29  4408.9  993.46  4428.2  991.90  4534.0  983.33  4554.5  980.08
  4600.8  978.12  4609.0  975.99  4630.9  974.77  4641.8  976.31  4676.5  975.91
  4707.3  979.21  4746.6  980.52  4921.3  980.89  4944.6  979.52  4958.3  975.64
  4980.2  975.95  4994.4  974.10  4994.8  971.10  4999.0  971.10  4999.3  974.10
  5059.2  978.31  5091.8  977.68  5161.8  981.74  5331.9  982.03  5471.9  977.31
  5561.9  983.56  5651.9  985.77  5741.9  991.58  5849.7  994.90  5892.0  996.91
#Mann=7,-1,0
  4336.1    0.12       0  4408.9    0.05       0  4428.2    0.12       0
  4534.0    0.05       0  4994.4    0.05       0  4999.3    0.05       0
  5849.7    0.12       0
Bank Sta=4994.4,4999.3
Exp/Cntr=0.3,0.1

Type RM Length L Ch R = 1,15864,499,499,499
BEGIN DESCRIPTION:
SANDY CREEK 29.0
END DESCRIPTION:
XS GIS Cut Line= 3
      2877555.71     10240253.10      2877109.50     10240385.00
      2876305.68     10240753.11
#Sta/Elev= 30
  4534.7  987.52  4722.4  979.28  4826.7  970.81  4899.7  971.21  4920.6  974.55
  4943.5  975.23  4971.6  970.72  4991.1  969.45  4991.4  966.45  4995.7  966.45
  4996.1  969.45  5060.1  970.30  5092.2  970.44  5100.6  973.55  5106.1  971.96
  5114.2  976.20  5129.1  977.38  5170.9  977.64  5485.2  979.10  5499.1  978.54
  5513.7  973.78  5521.1  973.93  5559.7  977.75  5588.3  975.38  5605.8  978.39
  5686.1  985.33  5754.8  987.02  5772.3  988.96  5800.8  988.49  5884.1  992.80
#Mann=5,-1,0
  4534.7    0.05       0  4991.1    0.05       0  4996.1    0.05       0
  5060.1    0.12       0  5170.9    0.05       0
Bank Sta=4991.1,4996.1
Exp/Cntr=0.3,0.1

Type RM Length L Ch R = 1,15365,477,477,477
BEGIN DESCRIPTION:
SANDY CREEK 28.0
END DESCRIPTION:
XS GIS Cut Line= 3
      2877505.70     10239903.11      2877260.50     10239932.00
      2876455.70     10240553.10
#Sta/Elev= 30
  4753.1  981.77  4904.2  975.50  4924.3  972.73  4987.5  968.14  5011.2  967.51
  5032.0  969.10  5078.0  965.16  5078.5  962.16  5085.3  962.16  5085.8  965.16
  5096.3  968.24  5110.8  970.26  5154.3  973.04  5258.5  974.68  5344.3  973.95
  5384.0  974.29  5453.2  975.86  5608.6  974.32  5623.8  973.84  5667.0  973.93
  5675.2  970.95  5681.5  972.01  5688.2  969.68  5830.9  977.11  5888.9  977.64
  5895.2  975.13  5909.7  972.75  5953.2  975.02  5974.1  978.77  6016.6  981.90
#Mann=9,-1,0
  4753.1    0.05       0  4987.5    0.12       0  5078.0    0.07       0
  5085.8    0.12       0  5258.5    0.05       0  5344.3    0.12       0
  5384.0    0.05       0  5608.6    0.12       0  5623.8    0.05       0
Bank Sta=5078,5085.8
Exp/Cntr=0.3,0.1

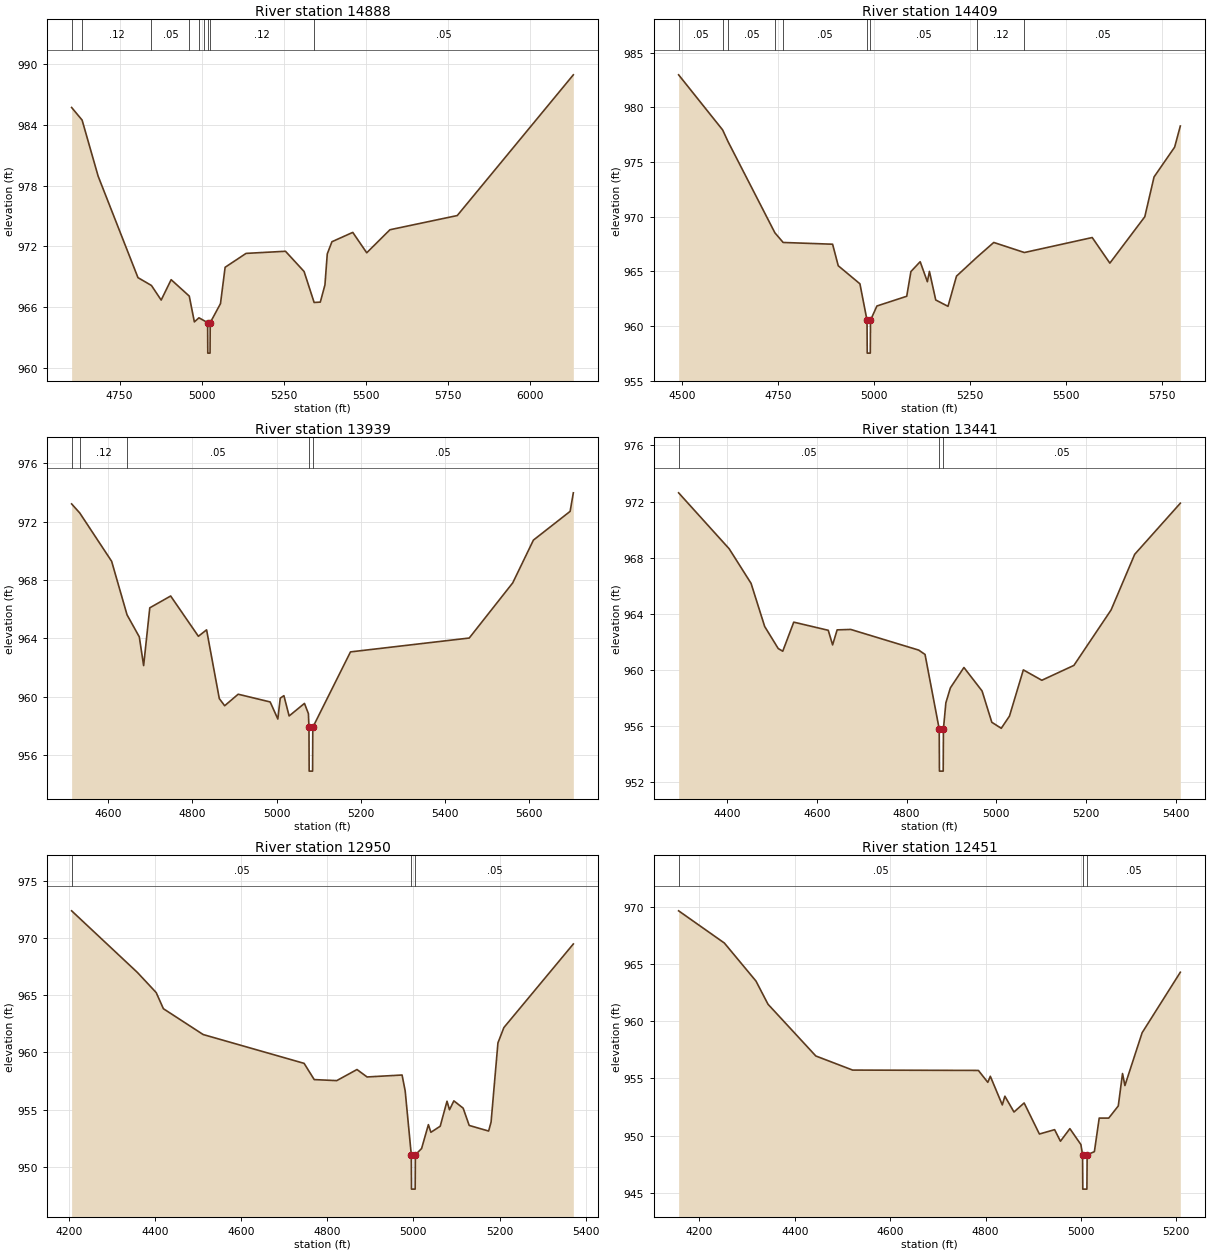
Type RM Length L Ch R = 1,14888,479,479,479
BEGIN DESCRIPTION:
SANDY CREEK 27.0
END DESCRIPTION:
XS GIS Cut Line= 3
      2877405.70     10239503.11      2877013.50     10239560.00
      2876205.67     10240353.13
#Sta/Elev= 30
  4603.7  985.69  4635.6  984.45  4684.5  978.92  4805.8  968.92  4846.8  968.15
  4876.5  966.71  4906.9  968.72  4962.1  967.10  4977.6  964.56  4991.6  964.96
  5006.1  964.70  5018.0  964.48  5018.5  961.48  5025.4  961.48  5025.9  964.48
  5057.2  966.36  5071.3  969.94  5135.1  971.31  5255.2  971.52  5311.8  969.53
  5342.5  966.47  5361.3  966.51  5375.4  968.20  5382.5  971.26  5396.7  972.46
  5460.2  973.38  5502.7  971.37  5573.4  973.64  5778.5  975.04  6132.1  988.91
#Mann=9,-1,0
  4603.7    0.05       0  4635.6    0.12       0  4846.8    0.05       0
  4962.1    0.12       0  4991.6    0.05       0  5006.1    0.12       0
  5018.0    0.05       0  5025.9    0.12       0  5342.5    0.05       0
Bank Sta=5018,5025.9
Exp/Cntr=0.3,0.1

Type RM Length L Ch R = 1,14409,470,470,470
BEGIN DESCRIPTION:
SANDY CREEK 26.0
END DESCRIPTION:
XS GIS Cut Line= 3
      2877405.71     10239403.13      2876994.75     10239104.00
      2876255.68     10239403.11
#Sta/Elev= 30
  4491.7  982.98  4606.3  977.94  4619.9  976.90  4742.3  968.53  4763.7  967.65
  4892.4  967.49  4907.1  965.52  4963.5  963.87  4982.0  960.53  4982.5  957.53
  4990.5  957.53  4991.0  960.53  5007.7  961.84  5085.3  962.73  5096.2  964.99
  5120.3  965.89  5139.0  964.06  5144.4  965.00  5160.8  962.39  5192.7  961.81
  5214.8  964.57  5267.1  966.27  5311.8  967.65  5391.5  966.73  5568.0  968.10
  5613.9  965.76  5704.8  970.00  5728.9  973.64  5782.5  976.37  5797.3  978.30
#Mann=9,-1,0
  4491.7    0.05       0  4606.3    0.12       0  4619.9    0.05       0
  4742.3    0.12       0  4763.7    0.05       0  4982.0    0.05       0
  4991.0    0.05       0  5267.1    0.12       0  5391.5    0.05       0
Bank Sta=4982,4991
Exp/Cntr=0.3,0.1

Type RM Length L Ch R = 1,13939,498,498,498
BEGIN DESCRIPTION:
SANDY CREEK 25.0
END DESCRIPTION:
XS GIS Cut Line= 3
      2877255.69     10238553.11      2876800.25     10238725.00
      2876205.69     10239103.11
#Sta/Elev= 30
  4513.2  973.21  4532.5  972.59  4608.2  969.28  4644.8  965.61  4673.9  964.10
  4684.2  962.13  4698.8  966.09  4748.4  966.90  4814.2  964.14  4833.7  964.58
  4863.9  959.87  4876.6  959.38  4908.7  960.17  4984.7  959.64  5002.9  958.47
  5008.6  959.90  5017.3  960.07  5029.7  958.68  5066.1  959.54  5075.5  958.84
  5076.8  957.90  5077.3  954.90  5085.4  954.90  5085.9  957.90  5175.4  963.07
  5457.4  964.02  5560.7  967.80  5609.8  970.73  5697.0  972.70  5704.6  973.97
#Mann=5,-1,0
  4513.2    0.05       0  4532.5    0.12       0  4644.8    0.05       0
  5076.8    0.03       0  5085.9    0.05       0
Bank Sta=5076.8,5085.9
Exp/Cntr=0.3,0.1

Type RM Length L Ch R = 1,13441,491,491,491
BEGIN DESCRIPTION:
SANDY CREEK 24.0
END DESCRIPTION:
XS GIS Cut Line= 3
      2877155.64     10238303.12      2876454.00     10238400.00
      2876055.71     10238303.12
#Sta/Elev= 30
  4291.7  972.62  4404.5  968.63  4453.2  966.17  4483.5  963.10  4513.7  961.53
  4523.8  961.34  4548.3  963.41  4625.2  962.83  4634.9  961.79  4645.0  962.86
  4675.3  962.89  4826.7  961.42  4840.9  961.11  4872.5  955.80  4873.0  952.80
  4881.4  952.80  4881.9  955.80  4887.3  957.66  4897.4  958.73  4927.6  960.18
  4968.0  958.51  4989.7  956.28  5010.8  955.85  5029.1  956.72  5060.0  960.01
  5101.2  959.27  5172.7  960.33  5255.6  964.28  5308.2  968.24  5409.9  971.88
#Mann=3,-1,0
  4291.7    0.05       0  4872.5    0.03       0  4881.9    0.05       0
Bank Sta=4872.5,4881.9
Exp/Cntr=0.3,0.1

Type RM Length L Ch R = 1,12950,499,499,499
BEGIN DESCRIPTION:
SANDY CREEK 23.0
END DESCRIPTION:
XS GIS Cut Line= 3
      2877155.73     10238253.13      2876428.25     10237937.00
      2876105.68     10237753.11
#Sta/Elev= 30
  4206.8  972.38  4359.5  966.99  4403.1  965.23  4419.8  963.82  4512.1  961.56
  4746.4  959.04  4769.9  957.62  4822.2  957.53  4869.1  958.50  4892.6  957.85
  4973.8  958.02  4981.0  956.63  4995.2  951.04  4995.7  948.04  5004.2  948.04
  5004.7  951.04  5019.1  951.59  5034.9  953.68  5040.7  953.01  5062.3  953.54
  5078.1  955.73  5083.9  954.98  5094.0  955.76  5115.6  955.12  5129.6  953.61
  5174.7  953.12  5180.4  953.91  5196.3  960.83  5210.1  962.17  5371.3  969.48
#Mann=3,-1,0
  4206.8    0.05       0  4995.2    0.05       0  5004.7    0.05       0
Bank Sta=4995.2,5004.7
Exp/Cntr=0.3,0.1

Type RM Length L Ch R = 1,12451,471,471,471
BEGIN DESCRIPTION:
SANDY CREEK 22.0
END DESCRIPTION:
XS GIS Cut Line= 3
      2877155.67     10237753.11      2876364.00     10237462.00
      2876155.69     10237453.11
#Sta/Elev= 30
  4156.5  969.63  4252.4  966.82  4318.7  963.50  4343.9  961.48  4444.2  956.96
  4521.4  955.73  4785.1  955.70  4804.8  954.66  4810.1  955.19  4835.2  952.69
  4840.6  953.45  4859.7  952.07  4881.0  952.86  4913.0  950.15  4944.9  950.53
  4957.1  949.52  4976.9  950.62  5000.0  949.23  5003.5  948.34  5004.0  945.34
  5012.6  945.34  5013.1  948.34  5028.3  948.61  5038.4  951.54  5058.4  951.54
  5078.4  952.60  5087.3  955.43  5092.3  954.38  5128.4  958.99  5208.5  964.27
#Mann=3,-1,0
  4156.5    0.05       0  5003.5    0.05       0  5013.1    0.05       0
Bank Sta=5003.5,5013.1
Exp/Cntr=0.3,0.1

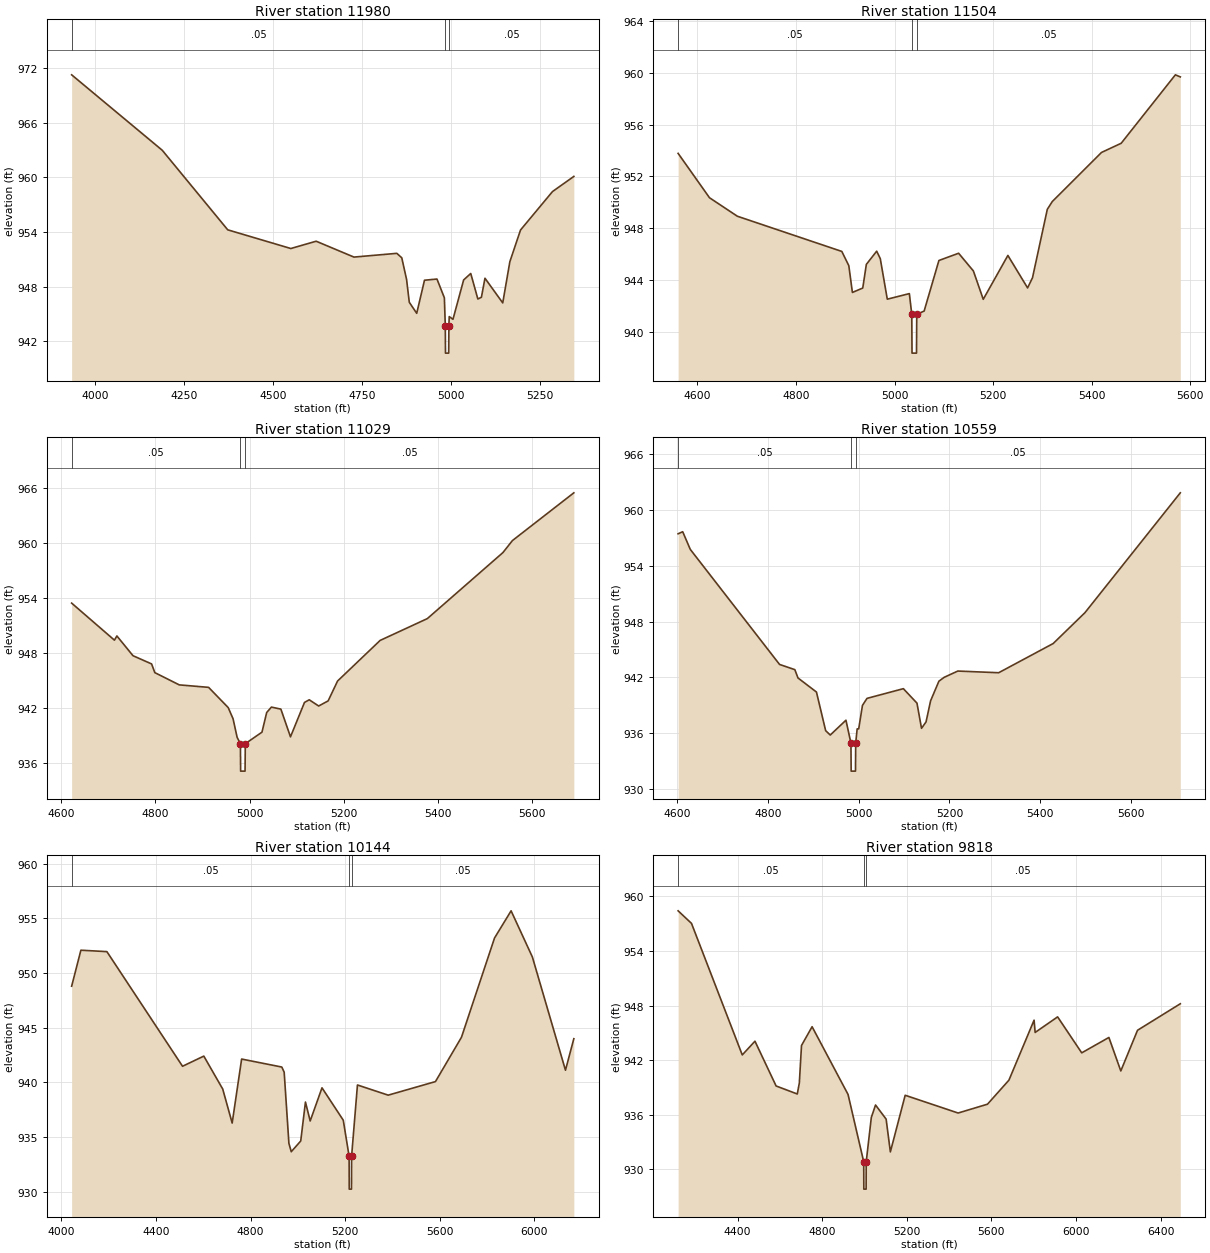
Type RM Length L Ch R = 1,11980,476,476,476
BEGIN DESCRIPTION:
SANDY CREEK 21.0
END DESCRIPTION:
XS GIS Cut Line= 3
      2877255.69     10237703.11      2876451.50     10237002.00
      2876105.70     10237003.11
#Sta/Elev= 30
  3933.1  971.24  4188.0  962.96  4372.2  954.23  4549.7  952.18  4620.9  952.98
  4727.2  951.24  4847.8  951.65  4861.8  951.16  4875.3  948.78  4882.9  946.28
  4903.8  945.07  4925.7  948.70  4960.8  948.83  4981.6  946.77  4984.2  943.70
  4984.7  940.70  4993.8  940.70  4994.3  943.70  4995.3  944.71  5005.8  944.41
  5035.8  948.73  5055.8  949.44  5075.8  946.64  5085.8  946.83  5095.8  948.92
  5145.8  946.21  5165.8  950.73  5195.8  954.21  5285.8  958.43  5345.8  960.09
#Mann=3,-1,0
  3933.1    0.05       0  4984.2    0.03       0  4994.3    0.05       0
Bank Sta=4984.2,4994.3
Exp/Cntr=0.3,0.1

Type RM Length L Ch R = 1,11504,475,475,475
BEGIN DESCRIPTION:
SANDY CREEK 20.0
END DESCRIPTION:
XS GIS Cut Line= 3
      2877005.65     10236903.08      2876685.75     10236602.00
      2876105.65     10236603.11
#Sta/Elev= 30
  4560.7  953.78  4624.4  950.35  4681.0  948.92  4893.0  946.20  4907.2  945.10
  4914.5  943.03  4935.5  943.37  4942.8  945.20  4963.8  946.22  4971.1  945.64
  4985.3  942.51  5030.1  942.94  5035.0  941.34  5035.5  938.34  5044.6  938.34
  5045.1  941.34  5060.1  941.59  5090.1  945.50  5130.1  946.06  5160.1  944.69
  5180.1  942.50  5230.1  945.89  5270.1  943.38  5280.1  944.17  5310.1  949.45
  5320.1  950.05  5420.1  953.85  5460.1  954.56  5570.1  959.85  5580.1  959.69
#Mann=3,-1,0
  4560.7    0.05       0  5035.0    0.03       0  5045.1    0.05       0
Bank Sta=5035,5045.1
Exp/Cntr=0.3,0.1

Type RM Length L Ch R = 1,11029,470,470,470
BEGIN DESCRIPTION:
SANDY CREEK 19.0
END DESCRIPTION:
XS GIS Cut Line= 3
      2877055.71     10236253.12      2876692.00     10236152.00
      2876005.70     10236203.11
#Sta/Elev= 30
  4622.5  953.45  4713.3  949.40  4718.5  949.86  4752.7  947.70  4792.2  946.80
  4799.0  945.85  4850.9  944.51  4913.1  944.24  4954.7  942.03  4965.0  940.81
  4973.7  938.77  4980.6  938.08  4981.1  935.08  4990.5  935.08  4991.0  938.08
  5026.4  939.34  5036.4  941.49  5046.4  942.08  5066.5  941.86  5086.9  938.83
  5116.6  942.59  5126.7  942.88  5146.7  942.20  5166.8  942.76  5186.8  944.93
  5277.1  949.37  5377.4  951.76  5537.8  958.98  5557.9  960.29  5688.2  965.51
#Mann=3,-1,0
  4622.5    0.05       0  4980.6    0.03       0  4991.0    0.05       0
Bank Sta=4980.6,4991
Exp/Cntr=0.3,0.1

Type RM Length L Ch R = 1,10559,415,415,415
BEGIN DESCRIPTION:
SANDY CREEK 18.0
END DESCRIPTION:
XS GIS Cut Line= 3
      2877105.67     10235753.11      2876714.00     10235683.00
      2876005.69     10235703.11
#Sta/Elev= 30
  4602.1  957.41  4612.2  957.63  4629.0  955.73  4825.6  943.40  4859.3  942.84
  4866.2  941.95  4906.9  940.44  4927.2  936.30  4937.3  935.83  4971.9  937.42
  4982.9  934.96  4983.4  931.96  4992.9  931.96  4993.4  934.96  4996.6  936.49
  5000.0  936.49  5008.3  939.01  5018.3  939.76  5098.4  940.80  5128.4  939.25
  5138.4  936.55  5148.4  937.24  5158.4  939.50  5176.7  941.60  5188.4  942.02
  5218.4  942.69  5308.4  942.51  5428.5  945.64  5498.5  948.95  5708.6  961.80
#Mann=3,-1,0
  4602.1    0.05       0  4982.9    0.05       0  4993.4    0.05       0
Bank Sta=4982.9,4993.4
Exp/Cntr=0.3,0.1

Type RM Length L Ch R = 1,10144,326,326,326
BEGIN DESCRIPTION:
Mapping XS ae5aaec2
END DESCRIPTION:
XS GIS Cut Line= 3
      2877784.75     10235291.33      2876555.61     10235291.33
      2875660.25     10235291.33
#Sta/Elev= 30
  4043.3  948.79  4082.4  952.08  4192.4  951.95  4512.4  941.47  4602.4  942.40
  4682.4  939.39  4722.4  936.28  4762.4  942.13  4932.4  941.40  4942.4  940.93
  4962.4  934.42  4972.4  933.66  5012.4  934.64  5032.4  938.20  5052.4  936.47
  5102.4  939.50  5192.4  936.54  5217.1  933.24  5217.6  930.24  5227.1  930.24
  5227.6  933.24  5252.4  939.76  5382.4  938.83  5582.4  940.07  5692.4  944.12
  5832.4  953.20  5902.4  955.68  5992.4  951.46  6132.4  941.11  6167.8  943.99
#Mann=3,-1,0
  4043.3    0.05       0  5217.1    0.03       0  5227.6    0.05       0
Bank Sta=5217.1,5227.6
Exp/Cntr=0.3,0.1

Type RM Length L Ch R = 1,9818,433,433,433
BEGIN DESCRIPTION:
Mapping XS 619bc3f0
END DESCRIPTION:
XS GIS Cut Line= 4
      2877638.94     10234999.67      2876597.27     10234978.83
      2875680.61     10235020.50      2875348.84     10235269.33
#Sta/Elev= 30
  4119.2  958.41  4182.5  957.03  4422.5  942.58  4482.5  944.09  4582.5  939.17
  4682.6  938.29  4692.3  939.50  4702.6  943.62  4752.6  945.68  4922.6  938.24
  4996.7  930.84  4997.2  927.84  5008.0  927.84  5008.5  930.84  5032.6  935.71
  5052.6  937.08  5102.6  935.53  5122.7  931.93  5192.7  938.15  5443.0  936.20
  5581.9  937.17  5683.2  939.81  5802.1  946.40  5807.1  945.05  5913.4  946.76
  6027.3  942.81  6155.8  944.50  6212.1  940.82  6291.2  945.29  6493.4  948.20
#Mann=3,-1,0
  4119.2    0.05       0  4996.7    0.05       0  5008.5    0.05       0
Bank Sta=4996.7,5008.5
Exp/Cntr=0.3,0.1

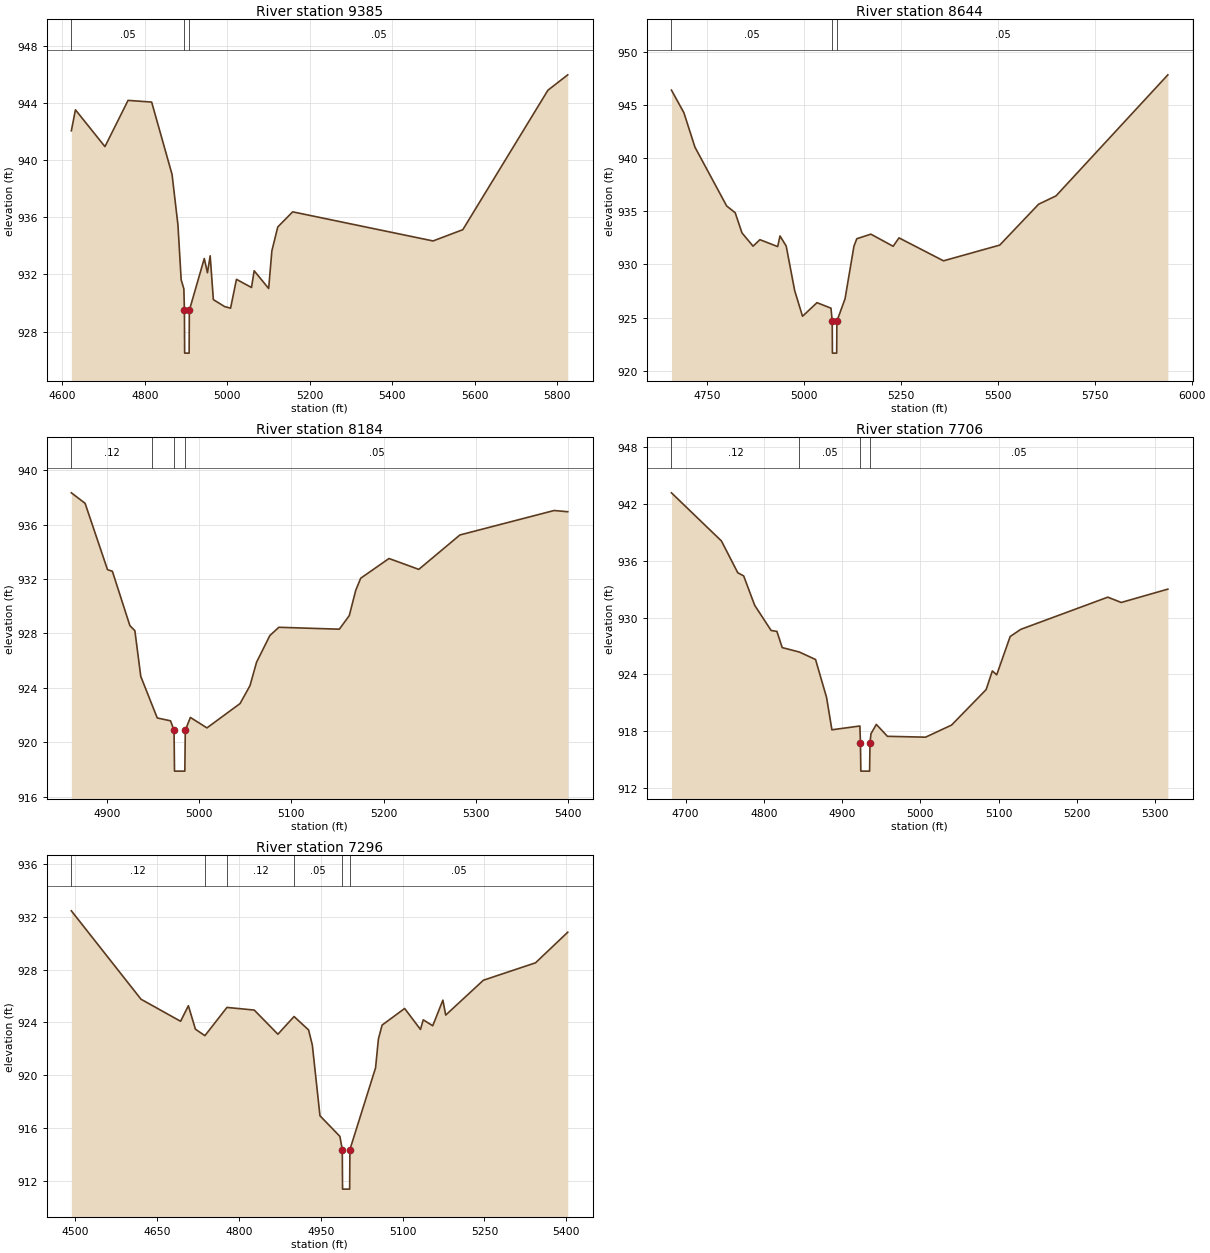
Type RM Length L Ch R = 1,9385,741,741,741
BEGIN DESCRIPTION:
Mapping XS b08d1f7f
END DESCRIPTION:
XS GIS Cut Line= 3
      2876909.79     10234332.98      2876513.94     10234666.33
      2875849.02     10234832.56
#Sta/Elev= 30
  4622.2  942.07  4632.1  943.54  4703.6  940.96  4759.6  944.20  4816.8  944.08
  4866.2  939.01  4880.5  935.47  4888.3  931.63  4894.8  931.00  4896.2  929.49
  4896.7  926.49  4907.6  926.49  4908.1  929.49  4944.3  933.12  4952.0  932.12
  4958.6  933.31  4966.3  930.24  4993.7  929.75  5008.0  929.64  5022.3  931.66
  5058.7  931.09  5065.2  932.26  5100.3  931.02  5108.1  933.66  5122.4  935.33
  5158.5  936.39  5498.7  934.35  5570.8  935.14  5777.0  944.91  5825.1  945.99
#Mann=3,-1,0
  4622.2    0.05       0  4896.2    0.05       0  4908.1    0.05       0
Bank Sta=4896.2,4908.1
Exp/Cntr=0.3,0.1

Type RM Length L Ch R = 1,8644,460,460,460
BEGIN DESCRIPTION:
SANDY CREEK 14.0
END DESCRIPTION:
XS GIS Cut Line= 3
      2876355.67     10233653.15      2876215.50     10233965.00
      2875705.70     10234753.08
#Sta/Elev= 30
  4658.1  946.41  4690.1  944.29  4718.7  941.04  4800.6  935.50  4822.5  934.87
  4840.0  932.97  4868.6  931.72  4886.3  932.33  4932.1  931.68  4938.1  932.68
  4954.1  931.73  4976.0  927.53  4996.2  925.12  5033.5  926.40  5069.6  925.88
  5072.8  924.65  5073.3  921.65  5084.3  921.65  5084.8  924.65  5105.9  926.77
  5128.8  931.71  5136.2  932.42  5172.5  932.85  5229.9  931.71  5245.1  932.50
  5359.8  930.34  5504.9  931.82  5605.2  935.67  5650.0  936.45  5938.6  947.85
#Mann=3,-1,0
  4658.1    0.05       0  5072.8    0.05       0  5084.8    0.05       0
Bank Sta=5072.8,5084.8
Exp/Cntr=0.3,0.1

Type RM Length L Ch R = 1,8184,478,478,478
BEGIN DESCRIPTION:
SANDY CREEK 13.0
END DESCRIPTION:
XS GIS Cut Line= 3
      2875855.69     10233653.09      2875804.50     10233782.00
      2875655.70     10234153.08
#Sta/Elev= 30
  4861.3  938.34  4876.2  937.57  4900.5  932.69  4905.8  932.57  4924.8  928.57
  4930.2  928.20  4936.6  924.84  4948.8  922.75  4954.5  921.78  4968.9  921.57
  4972.7  920.87  4973.2  917.87  4984.4  917.87  4984.9  920.87  4990.4  921.82
  5008.4  921.05  5044.3  922.84  5055.1  924.16  5062.2  925.88  5076.6  927.84
  5086.4  928.45  5152.0  928.31  5162.8  929.31  5169.8  931.17  5175.2  932.06
  5205.9  933.51  5238.2  932.71  5282.8  935.24  5385.0  937.04  5399.8  936.95
#Mann=4,-1,0
  4861.3    0.12       0  4948.8    0.05       0  4972.7    0.05       0
  4984.9    0.05       0
Bank Sta=4972.7,4984.9
Exp/Cntr=0.3,0.1

Type RM Length L Ch R = 1,7706,410,410,410
BEGIN DESCRIPTION:
SANDY CREEK 12.0
END DESCRIPTION:
XS GIS Cut Line= 3
      2875605.70     10233453.10      2875370.25     10233667.00
      2875505.66     10233953.07
#Sta/Elev= 30
  4681.9  943.18  4745.8  938.09  4766.7  934.73  4774.2  934.40  4788.3  931.29
  4809.3  928.63  4816.7  928.53  4823.5  926.82  4845.4  926.35  4866.1  925.56
  4880.2  921.55  4887.0  918.13  4922.8  918.53  4923.5  916.76  4924.0  913.76
  4935.2  913.76  4935.7  916.76  4937.0  917.72  4943.8  918.70  4958.0  917.44
  5006.8  917.35  5040.0  918.63  5084.2  922.38  5092.1  924.35  5097.7  923.94
  5114.9  927.99  5128.5  928.75  5239.7  932.15  5256.9  931.59  5316.5  933.00
#Mann=4,-1,0
  4681.9    0.12       0  4845.4    0.05       0  4923.5    0.03       0
  4935.7    0.05       0
Bank Sta=4923.5,4935.7
Exp/Cntr=0.3,0.1

Type RM Length L Ch R = 1,7296,499,499,499
BEGIN DESCRIPTION:
SANDY CREEK 11.0
END DESCRIPTION:
XS GIS Cut Line= 3
      2875305.68     10233203.12      2874996.25     10233605.00
      2874605.68     10233703.11
#Sta/Elev= 30
  4492.8  932.46  4620.5  925.76  4693.0  924.09  4707.3  925.27  4720.2  923.49
  4737.6  923.00  4778.0  925.14  4828.0  924.94  4871.4  923.11  4901.0  924.45
  4927.7  923.43  4934.5  922.29  4948.5  916.93  4985.0  915.37  4989.4  914.37
  4989.9  911.37  5002.9  911.37  5003.4  914.37  5050.4  920.56  5055.6  922.74
  5062.4  923.80  5103.7  925.06  5132.7  923.47  5137.8  924.20  5155.2  923.75
  5173.8  925.69  5179.0  924.56  5248.0  927.20  5343.6  928.52  5402.7  930.84
#Mann=6,-1,0
  4492.8    0.12       0  4737.6    0.05       0  4778.0    0.12       0
  4901.0    0.05       0  4989.4    0.05       0  5003.4    0.05       0
Bank Sta=4989.4,5003.4
Exp/Cntr=0.3,0.1