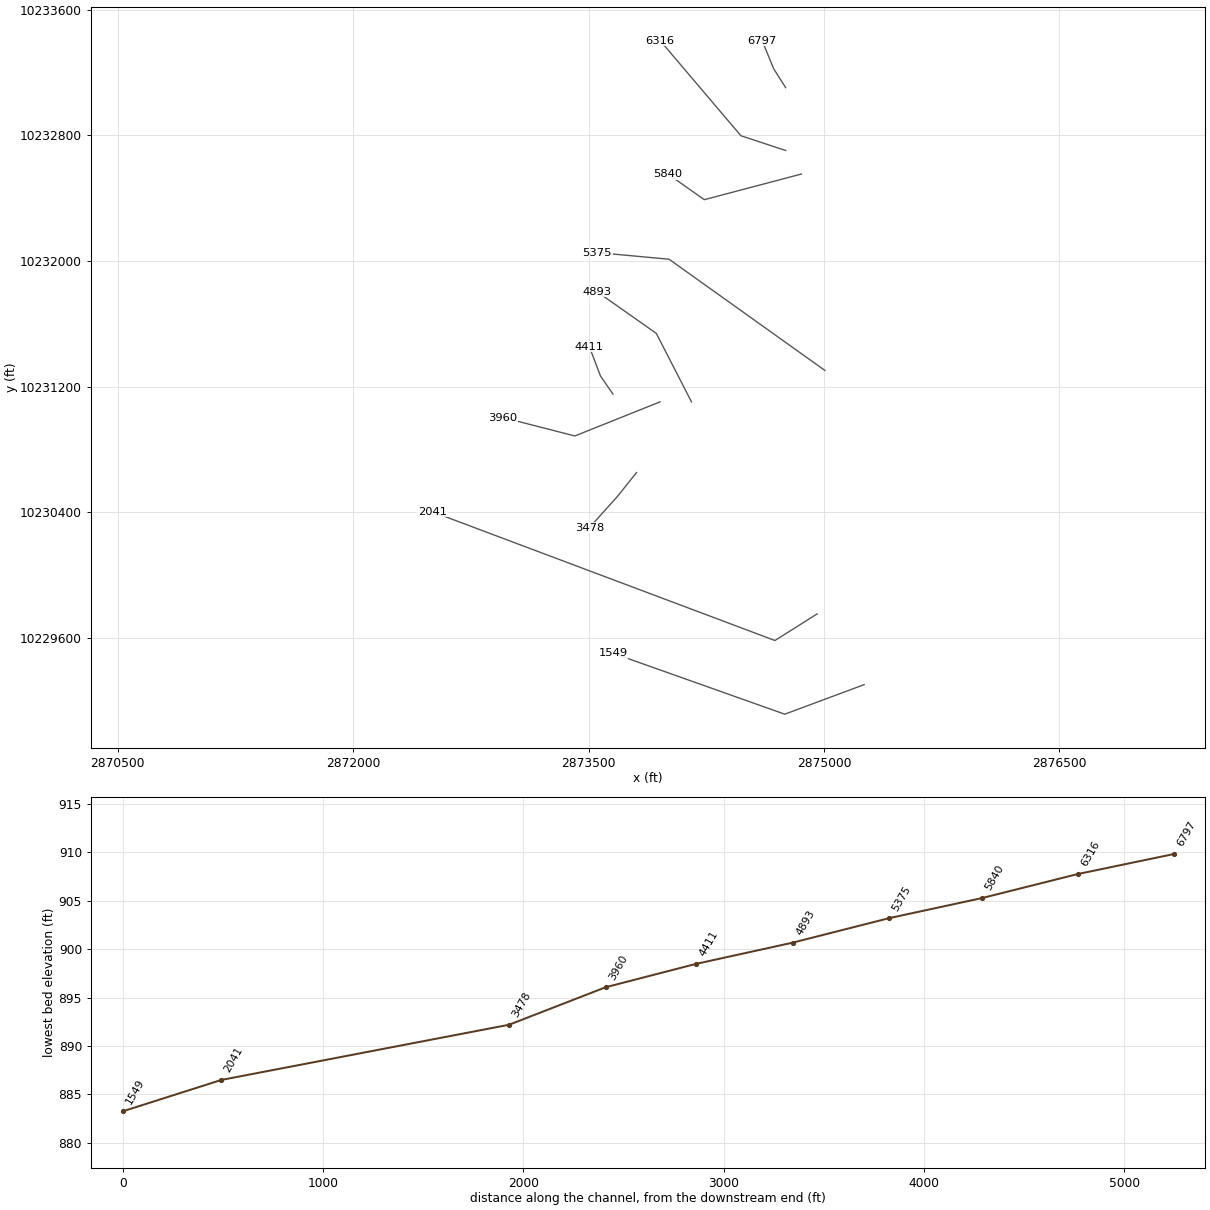
HEC-RAS study SANDY CREEK.prj: SANDY CREEK Base Level Engineering

--- SANDY CREEK.g01 (geometry) --- (continued)

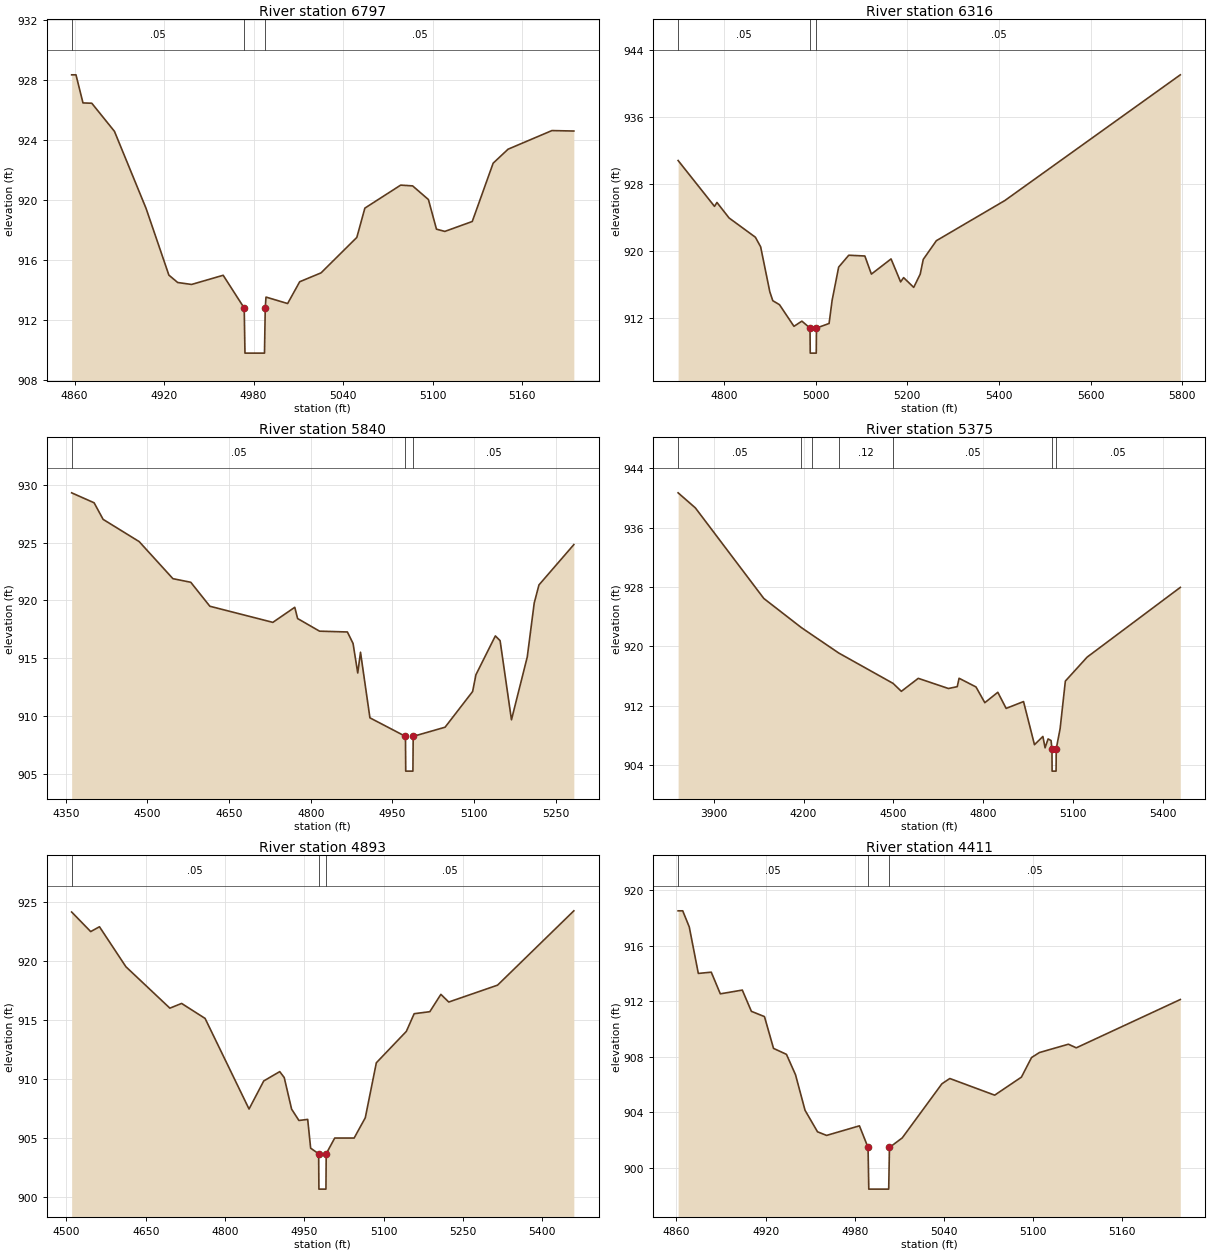
Type RM Length L Ch R = 1,6797,481,481,481
BEGIN DESCRIPTION:
SANDY CREEK 10.0
END DESCRIPTION:
XS GIS Cut Line= 3
      2874755.66     10233103.15      2874679.50     10233223.00
      2874605.67     10233403.16
#Sta/Elev= 30
  4858.0  928.33  4860.9  928.33  4865.6  926.46  4871.5  926.44  4886.7  924.57
  4907.9  919.44  4923.2  915.00  4929.1  914.51  4938.4  914.38  4959.6  914.99
  4973.7  912.81  4974.2  909.81  4987.3  909.81  4987.8  912.81  4988.3  913.54
  5002.8  913.11  5010.9  914.56  5025.2  915.15  5049.2  917.51  5054.6  919.46
  5078.6  920.99  5086.6  920.94  5097.2  920.03  5102.6  918.06  5108.2  917.91
  5126.6  918.57  5140.6  922.45  5150.6  923.38  5180.0  924.62  5194.7  924.59
#Mann=3,-1,0
  4858.0    0.05       0  4973.7    0.03       0  4987.8    0.05       0
Bank Sta=4973.7,4987.8
Exp/Cntr=0.3,0.1

Type RM Length L Ch R = 1,6316,476,476,476
BEGIN DESCRIPTION:
SANDY CREEK 9.0
END DESCRIPTION:
XS GIS Cut Line= 3
      2874755.68     10232703.11      2874470.75     10232797.00
      2873955.69     10233403.11
#Sta/Elev= 30
  4700.0  930.80  4779.4  925.31  4784.7  925.78  4811.2  923.92  4868.5  921.62
  4880.0  920.47  4900.0  915.09  4906.5  914.02  4921.1  913.54  4952.7  910.95
  4970.0  911.57  4987.7  910.74  4988.2  907.74  5001.3  907.74  5001.8  910.74
  5029.3  911.29  5035.9  914.05  5050.2  918.04  5072.2  919.46  5107.3  919.37
  5121.6  917.20  5164.5  919.02  5185.3  916.27  5191.9  916.78  5213.9  915.61
  5228.1  917.20  5234.7  918.96  5263.3  921.20  5412.7  926.01  5795.4  941.06
#Mann=3,-1,0
  4700.0    0.05       0  4987.7    0.05       0  5001.8    0.05       0
Bank Sta=4987.7,5001.8
Exp/Cntr=0.3,0.1

Type RM Length L Ch R = 1,5840,465,465,465
BEGIN DESCRIPTION:
SANDY CREEK 8.0
END DESCRIPTION:
XS GIS Cut Line= 3
      2874855.64     10232553.10      2874237.50     10232390.00
      2874005.64     10232553.14
#Sta/Elev= 30
  4360.7  929.29  4402.0  928.43  4418.5  927.00  4484.8  925.08  4546.8  921.88
  4579.6  921.57  4614.7  919.50  4730.4  918.11  4770.7  919.41  4775.9  918.44
  4816.2  917.35  4867.4  917.28  4877.8  916.29  4886.4  913.74  4891.5  915.53
  4908.8  909.87  4974.1  908.27  4974.6  905.27  4987.8  905.27  4988.3  908.27
  5046.9  909.06  5097.5  912.14  5103.6  913.59  5139.3  916.94  5148.0  916.53
  5168.9  909.70  5197.9  915.12  5210.7  919.78  5219.4  921.34  5283.5  924.82
#Mann=3,-1,0
  4360.7    0.05       0  4974.1    0.05       0  4988.3    0.05       0
Bank Sta=4974.1,4988.3
Exp/Cntr=0.3,0.1

Type RM Length L Ch R = 1,5375,482,482,482
BEGIN DESCRIPTION:
SANDY CREEK 7.0
END DESCRIPTION:
XS GIS Cut Line= 3
      2875005.66     10231303.13      2874013.00     10232011.00
      2873555.64     10232053.12
#Sta/Elev= 30
  3780.8  940.68  3838.5  938.65  4067.2  926.45  4192.6  922.53  4226.7  921.59
  4317.7  919.10  4499.3  915.01  4526.9  913.94  4583.5  915.69  4684.3  914.32
  4713.8  914.57  4719.9  915.70  4776.4  914.53  4805.9  912.41  4849.3  913.81
  4877.2  911.64  4935.3  912.56  4971.9  906.75  5000.0  907.86  5007.3  906.33
  5017.4  907.53  5027.4  907.31  5030.3  906.19  5030.8  903.19  5044.1  903.19
  5044.6  906.19  5057.6  908.91  5075.1  915.32  5147.9  918.55  5459.3  927.94
#Mann=7,-1,0
  3780.8    0.05       0  4192.6    0.12       0  4226.7    0.05       0
  4317.7    0.12       0  4499.3    0.05       0  5030.3    0.05       0
  5044.6    0.05       0
Bank Sta=5030.3,5044.6
Exp/Cntr=0.3,0.1

Type RM Length L Ch R = 1,4893,482,482,482
BEGIN DESCRIPTION:
SANDY CREEK 6.0
END DESCRIPTION:
XS GIS Cut Line= 3
      2874155.66     10231103.15      2873931.75     10231539.00
      2873555.72     10231803.09
#Sta/Elev= 30
  4510.0  924.15  4546.0  922.49  4562.6  922.90  4612.6  919.51  4695.7  916.00
  4717.9  916.40  4762.3  915.13  4845.4  907.45  4873.2  909.83  4903.4  910.62
  4911.9  910.12  4925.9  907.44  4939.7  906.48  4956.3  906.57  4961.9  904.13
  4977.0  903.66  4977.5  900.66  4990.8  900.66  4991.3  903.66  5007.4  904.99
  5044.1  904.99  5065.2  906.71  5086.1  911.37  5142.8  914.03  5157.6  915.53
  5187.2  915.70  5208.1  917.17  5223.0  916.52  5315.3  917.95  5459.5  924.25
#Mann=3,-1,0
  4510.0    0.05       0  4977.0    0.03       0  4991.3    0.05       0
Bank Sta=4977,4991.3
Exp/Cntr=0.3,0.1

Type RM Length L Ch R = 1,4411,451,451,451
BEGIN DESCRIPTION:
SANDY CREEK 5.0
END DESCRIPTION:
XS GIS Cut Line= 3
      2873655.71     10231153.07      2873576.25     10231267.00
      2873505.70     10231453.07
#Sta/Elev= 30
  4861.1  918.52  4864.2  918.52  4868.6  917.36  4874.7  914.01  4883.4  914.10
  4889.5  912.54  4904.3  912.81  4910.4  911.28  4919.2  910.90  4925.3  908.61
  4934.0  908.18  4940.1  906.71  4946.5  904.15  4954.9  902.60  4961.0  902.34
  4983.1  903.03  4988.9  901.47  4989.4  898.47  5002.8  898.47  5003.3  901.47
  5011.9  902.16  5038.6  906.06  5043.9  906.44  5074.1  905.24  5092.1  906.54
  5098.9  907.95  5104.2  908.31  5123.7  908.91  5129.0  908.65  5199.0  912.13
#Mann=3,-1,0
  4861.1    0.05       0  4988.9    0.03       0  5003.3    0.05       0
Bank Sta=4988.9,5003.3
Exp/Cntr=0.3,0.1

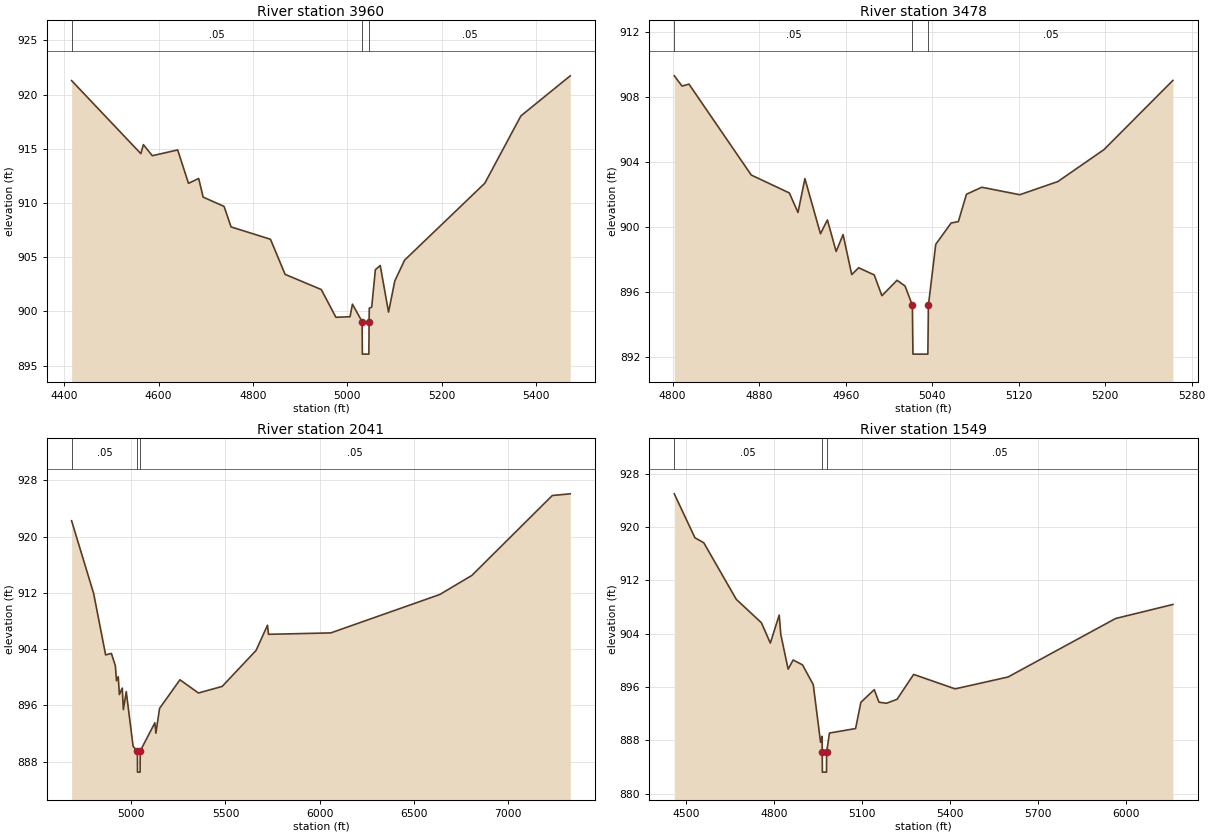
Type RM Length L Ch R = 1,3960,482,482,482
BEGIN DESCRIPTION:
SANDY CREEK 4.0
END DESCRIPTION:
XS GIS Cut Line= 3
      2873955.68     10231103.11      2873413.00     10230886.00
      2872955.66     10231003.12
#Sta/Elev= 30
  4415.5  921.30  4562.2  914.56  4567.6  915.39  4586.5  914.37  4640.3  914.90
  4663.2  911.82  4684.8  912.27  4694.2  910.55  4738.6  909.69  4753.4  907.80
  4836.9  906.66  4867.9  903.42  4944.6  902.02  4975.6  899.46  5005.5  899.51
  5010.6  900.67  5031.1  899.06  5031.6  896.06  5045.4  896.06  5045.9  899.06
  5046.3  900.30  5051.4  900.39  5059.2  903.85  5069.5  904.24  5087.1  899.94
  5100.5  902.83  5121.1  904.73  5291.1  911.83  5367.5  918.04  5472.1  921.74
#Mann=3,-1,0
  4415.5    0.05       0  5031.1    0.03       0  5045.9    0.05       0
Bank Sta=5031.1,5045.9
Exp/Cntr=0.3,0.1

Type RM Length L Ch R = 1,3478,1437,1437,1437
BEGIN DESCRIPTION:
SANDY CREEK 3.0
END DESCRIPTION:
XS GIS Cut Line= 3
      2873805.66     10230653.08      2873681.75     10230498.00
      2873505.71     10230303.14
#Sta/Elev= 30
  4801.5  909.30  4808.7  908.67  4815.1  908.79  4872.7  903.20  4907.9  902.10
  4915.9  900.90  4922.3  902.98  4936.7  899.59  4943.1  900.44  4951.2  898.50
  4957.6  899.54  4965.6  897.08  4972.0  897.50  4986.4  897.06  4993.5  895.78
  5007.5  896.73  5014.9  896.38  5021.7  895.19  5022.2  892.19  5036.0  892.19
  5036.5  895.19  5043.3  898.94  5057.5  900.25  5064.2  900.34  5071.7  902.02
  5085.9  902.45  5121.0  901.99  5156.2  902.80  5198.8  904.76  5262.6  909.02
#Mann=3,-1,0
  4801.5    0.05       0  5021.7    0.05       0  5036.5    0.05       0
Bank Sta=5021.7,5036.5
Exp/Cntr=0.3,0.1

Type RM Length L Ch R = 1,2041,492,492,492
BEGIN DESCRIPTION:
SANDY CREEK 2.0
END DESCRIPTION:
XS GIS Cut Line= 3
      2874955.73     10229753.14      2874687.50     10229584.00
      2872505.69     10230403.11
#Sta/Elev= 30
  4682.9  922.26  4800.0  911.91  4863.6  903.17  4894.2  903.38  4915.4  901.61
  4921.3  899.48  4930.7  900.07  4936.6  897.52  4951.9  898.45  4957.8  895.39
  4973.1  897.94  5009.5  890.16  5032.3  889.49  5032.8  886.49  5046.7  886.49
  5047.2  889.49  5125.1  893.51  5130.5  892.03  5150.0  895.56  5258.3  899.63
  5356.4  897.75  5482.6  898.69  5662.5  903.81  5723.0  907.39  5728.3  906.10
  6059.2  906.30  6637.5  911.76  6808.3  914.48  7235.3  925.85  7330.5  926.09
#Mann=3,-1,0
  4682.9    0.05       0  5032.3    0.05       0  5047.2    0.05       0
Bank Sta=5032.3,5047.2
Exp/Cntr=0.3,0.1

Type RM Length L Ch R = 1,1549,0,0,0
BEGIN DESCRIPTION:
SANDY CREEK 1.0
END DESCRIPTION:
XS GIS Cut Line= 3
      2875255.65     10229303.10      2874750.00     10229115.00
      2873655.69     10229503.11
#Sta/Elev= 30
  4460.5  925.00  4531.0  918.41  4561.3  917.65  4672.0  909.17  4757.7  905.66
  4788.1  902.61  4818.4  906.81  4823.8  903.91  4848.8  898.70  4865.9  900.07
  4897.9  899.34  4934.5  896.38  4959.5  887.72  4964.8  888.63  4965.1  886.25
  4965.6  883.25  4979.6  883.25  4980.1  886.25  4989.8  889.11  5078.9  889.79
  5096.9  893.72  5142.5  895.62  5158.7  893.74  5184.2  893.58  5220.4  894.18
  5276.9  897.91  5418.4  895.74  5598.8  897.52  5965.7  906.30  6161.1  908.40
#Mann=3,-1,0
  4460.5    0.05       0  4965.1    0.03       0  4980.1    0.05       0
Bank Sta=4965.1,4980.1
Exp/Cntr=0.3,0.1

Chan Stop Cuts=-1