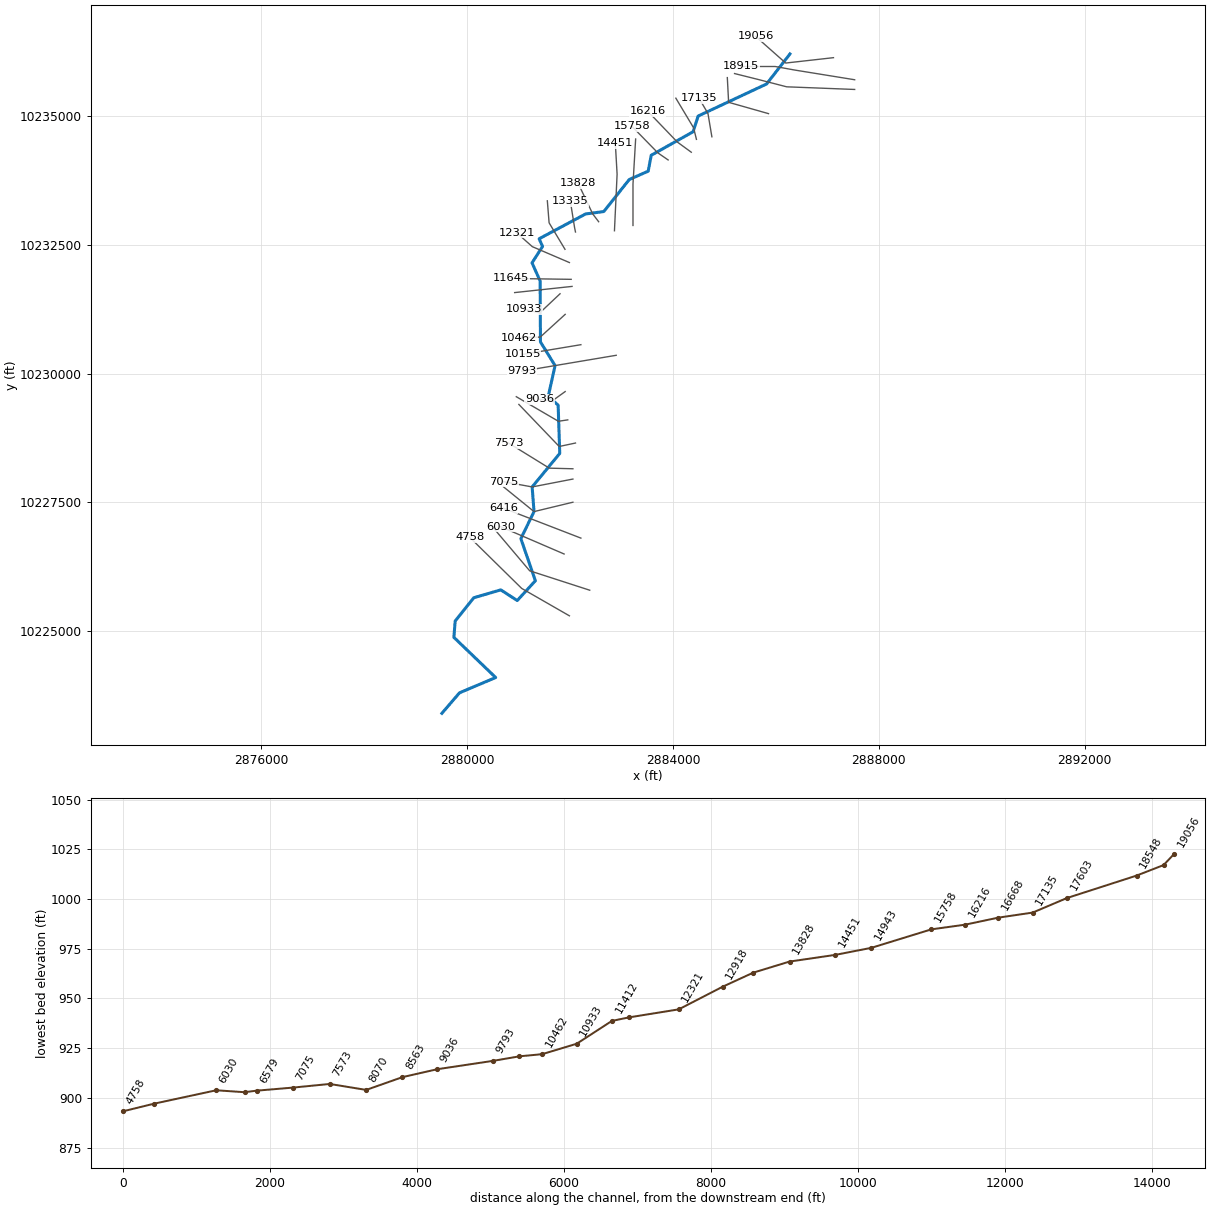
--- TANTROUGH CREEK.prj (project) ---

Proj Title=TANTROUGH CREEK Base Level Engineering
Current Plan=p01
Default Exp/Contr=0.3,0.1
English Units
Geom File=g01
Flow File=f01
Plan File=p01
BEGIN DESCRIPTION:
TANTROUGH CREEK
END DESCRIPTION:

--- TANTROUGH CREEK.p01 (plan) ---

Plan Title=Multiple Run
Short Identifier=Multiple
Geom File=g01
Flow File=f01
Subcritical Flow
K Sum by GR= 0
Std Step Tol= 0.01
Critical Tol= 0.01
Num of Std Step Trials= 20
Max Error Tol= 0.3
Flow Tol Ratio= 0.001
Split Flow NTrial= 30
Split Flow Tol= 0.02
Split Flow Ratio= 0.02
Log Output Level= 0
Friction Slope Method= 1
Unsteady Friction Slope Method= 2
Unsteady Bridges Friction Slope Method= 1
Parabolic Critical Depth
Global Vel Dist=  1 , 1 , 1
Global Log Level= 0
CheckData=True
Encroach Param= -1, 0, 0, 0
BEGIN DESCRIPTION:
Multiple Run
END DESCRIPTION:

--- TANTROUGH CREEK.f01 (steady flow) ---

Flow Title=Multiple
Number of Profiles=7
Profile Names=10-year,25-year,50-year,1pct_min,100-year,1pct_plu,500-year
River Rch & RM= TANTROUGH CREEK,Reach-1,19056
      66     126     197     102     308     930     809
River Rch & RM= TANTROUGH CREEK,Reach-1,11645
     107     219     353     187     565    1708    1553
River Rch & RM= TANTROUGH CREEK,Reach-1,9793
     131     276     450     242     730    2204    2040
Boundary for River Rch & Prof#=TANTROUGH CREEK,Reach-1,1
Up Type=0
Dn Type=3
Dn Slope=0.005
Boundary for River Rch & Prof#=TANTROUGH CREEK,Reach-1,2
Up Type=0
Dn Type=3
Dn Slope=0.005
Boundary for River Rch & Prof#=TANTROUGH CREEK,Reach-1,3
Up Type=0
Dn Type=3
Dn Slope=0.005
Boundary for River Rch & Prof#=TANTROUGH CREEK,Reach-1,4
Up Type=0
Dn Type=3
Dn Slope=0.005
Boundary for River Rch & Prof#=TANTROUGH CREEK,Reach-1,5
Up Type=0
Dn Type=3
Dn Slope=0.005
Boundary for River Rch & Prof#=TANTROUGH CREEK,Reach-1,6
Up Type=0
Dn Type=3
Dn Slope=0.005
Boundary for River Rch & Prof#=TANTROUGH CREEK,Reach-1,7
Up Type=0
Dn Type=3
Dn Slope=0.005

--- TANTROUGH CREEK.g01 (geometry) ---

Geom Title=Existing Conditions

River Reach=TANTROUGH CREEK,Reach-1
Reach XY= 30
      2886273.25     10236213.00      2885818.50     10235629.00
      2884488.75     10235006.00      2884390.75     10234701.00
      2883577.25     10234244.00      2883518.25     10233935.00
      2883150.25     10233773.00      2882656.25     10233151.00
      2882301.25     10233103.00      2881399.50     10232622.00
      2881465.75     10232472.00      2881261.00     10232154.00
      2881419.50     10231799.00      2881425.00     10230618.00
      2881709.25     10230157.00      2881576.25     10229560.00
      2881768.75     10229388.00      2881800.00     10228451.00
      2881263.50     10227800.00      2881300.00     10227321.00
      2881044.75     10226795.00      2881326.25     10225977.00
      2880974.00     10225593.00      2880654.25     10225800.00
      2880129.25     10225647.00      2879768.75     10225196.00
      2879742.75     10224878.00      2880555.25     10224097.00
      2879852.25     10223800.00      2879510.50     10223402.00

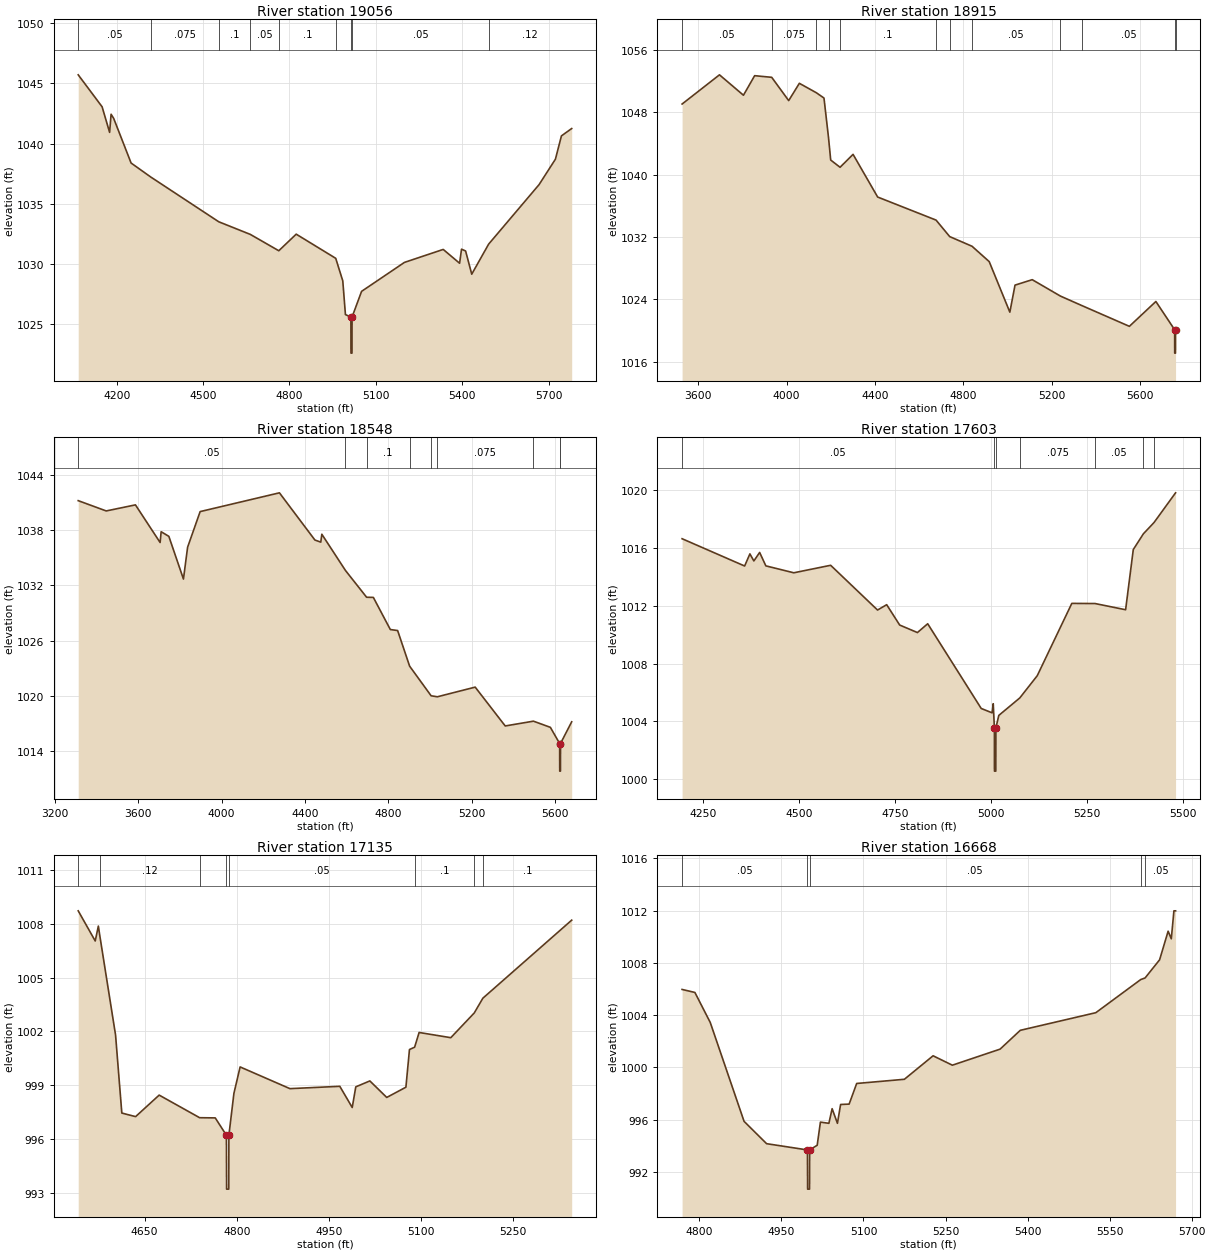
Type RM Length L Ch R = 1,19056,141,141,141
BEGIN DESCRIPTION:
TANTROUGH CREEK 37.0
END DESCRIPTION:
XS GIS Cut Line= 3
      2887118.19     10236140.42      2886190.25     10236036.00
      2885605.66     10236553.14
#Sta/Elev= 30
  4066.2 1045.72  4149.2 1043.06  4175.3 1040.93  4180.4 1042.44  4189.5 1042.09
  4249.9 1038.38  4318.6 1037.21  4554.5 1033.49  4664.1 1032.44  4763.0 1031.08
  4823.5 1032.46  4960.8 1030.45  4985.3 1028.57  4994.5 1025.77  5013.5 1025.56
  5013.8 1022.56  5017.3 1022.56  5017.5 1025.56  5050.6 1027.70  5199.5 1030.11
  5334.2 1031.19  5391.1 1030.04  5397.8 1031.21  5412.0 1031.06  5433.3 1029.13
  5492.0 1031.63  5667.1 1036.58  5724.0 1038.70  5744.9 1040.64  5780.5 1041.25
#Mann=9,-1,0
  4066.2    0.05       0  4318.6   0.075       0  4554.5     0.1       0
  4664.1    0.05       0  4763.0     0.1       0  4960.8    0.05       0
  5013.5    0.05       0  5017.5    0.05       0  5492.0    0.12       0
Bank Sta=5013.5,5017.5
Exp/Cntr=0.3,0.1

Type RM Length L Ch R = 1,18915,367,367,367
BEGIN DESCRIPTION:
Mapping XS c9c0759a
END DESCRIPTION:
XS GIS Cut Line= 4
      2887530.02     10235711.44      2886363.20     10235900.19
      2885985.70     10235968.83      2885316.48     10235968.83
#Sta/Elev= 30
  3526.7 1049.08  3696.0 1052.83  3804.6 1050.21  3855.3 1052.72  3932.6 1052.51
  4009.5 1049.52  4057.8 1051.74  4134.1 1050.54  4169.3 1049.85  4189.9 1044.75
  4199.7 1041.89  4242.1 1040.96  4301.0 1042.62  4412.4 1037.14  4676.8 1034.18
  4738.7 1032.06  4839.8 1030.82  4917.6 1028.85  5011.1 1022.36  5034.5 1025.83
  5112.4 1026.53  5240.4 1024.42  5337.7 1023.20  5552.4 1020.54  5672.4 1023.73
  5757.5 1020.10  5757.7 1017.10  5761.2 1017.10  5761.5 1020.10  5761.6 1020.10
#Mann=12,-1,0
  3526.7    0.05       0  3932.6   0.075       0  4134.1     0.1       0
  4189.9   0.075       0  4242.1     0.1       0  4676.8    0.05       0
  4738.7     0.1       0  4839.8    0.05       0  5240.4   0.075       0
  5337.7    0.05       0  5757.5    0.03       0  5761.5    0.05       0
Bank Sta=5757.5,5761.5
Exp/Cntr=0.3,0.1

Type RM Length L Ch R = 1,18548,945,945,945
BEGIN DESCRIPTION:
Mapping XS e5c717d1
END DESCRIPTION:
XS GIS Cut Line= 4
      2887530.01     10235522.70      2886208.77     10235574.17
      2885676.84     10235711.45      2885196.42     10235831.55
#Sta/Elev= 30
  3312.3 1041.21  3446.6 1040.09  3586.8 1040.75  3705.1 1036.66  3710.1 1037.83
  3747.0 1037.33  3817.0 1032.69  3837.0 1036.15  3897.1 1040.02  4277.4 1042.06
  4447.5 1036.93  4475.7 1036.70  4480.7 1037.56  4594.1 1033.62  4695.5 1030.71
  4727.9 1030.69  4809.3 1027.20  4844.3 1027.09  4901.8 1023.22  5004.9 1020.00
  5034.7 1019.89  5216.3 1020.94  5360.3 1016.72  5495.7 1017.24  5576.8 1016.57
  5621.4 1014.81  5621.7 1011.81  5625.2 1011.81  5625.4 1014.81  5679.1 1017.17
#Mann=9,-1,0
  3312.3    0.05       0  4594.1   0.075       0  4695.5     0.1       0
  4901.8    0.05       0  5004.9    0.12       0  5034.7   0.075       0
  5495.7    0.05       0  5621.4    0.05       0  5625.4    0.05       0
Bank Sta=5621.4,5625.4
Exp/Cntr=0.3,0.1

Type RM Length L Ch R = 1,17603,468,468,468
BEGIN DESCRIPTION:
TANTROUGH CREEK 34.0
END DESCRIPTION:
XS GIS Cut Line= 3
      2885855.70     10235053.11      2885081.00     10235273.00
      2885055.68     10235753.13
#Sta/Elev= 30
  4194.7 1016.65  4357.7 1014.76  4371.4 1015.60  4381.8 1015.11  4396.8 1015.70
  4413.0 1014.77  4485.8 1014.29  4581.9 1014.81  4704.1 1011.71  4727.9 1012.08
  4761.8 1010.67  4808.0 1010.15  4834.8 1010.76  4974.3 1004.89  5002.6 1004.59
  5005.6 1005.22  5008.6 1003.55  5008.8 1000.55  5012.3 1000.55  5012.6 1003.55
  5020.1 1004.41  5074.8 1005.62  5120.3 1007.16  5210.4 1012.17  5271.1 1012.16
  5350.6 1011.73  5370.6 1015.90  5396.9 1016.99  5424.6 1017.77  5480.8 1019.83
#Mann=7,-1,0
  4194.7    0.05       0  5008.6    0.05       0  5012.6    0.05       0
  5074.8   0.075       0  5271.1    0.05       0  5396.9     0.1       0
  5424.6    0.05       0
Bank Sta=5008.6,5012.6
Exp/Cntr=0.3,0.1

Type RM Length L Ch R = 1,17135,467,467,467
BEGIN DESCRIPTION:
TANTROUGH CREEK 33.0
END DESCRIPTION:
XS GIS Cut Line= 3
      2884755.68     10234603.14      2884679.75     10235055.00
      2884505.69     10235353.10
#Sta/Elev= 30
  4541.8 1008.72  4569.5 1007.04  4574.6 1007.87  4576.7 1007.39  4602.6 1001.80
  4612.8  997.45  4635.2  997.25  4673.6  998.45  4739.5  997.19  4764.9  997.18
  4783.1  996.21  4783.4  993.21  4786.9  993.21  4787.1  996.21  4795.3  998.55
  4805.4 1000.02  4886.5  998.81  4967.7  998.94  4987.9  997.76  4993.7  998.91
  5016.6  999.24  5044.1  998.32  5075.3  998.89  5081.1 1000.99  5089.5 1001.12
  5096.8 1001.94  5148.4 1001.65  5186.6 1003.03  5200.6 1003.85  5345.2 1008.20
#Mann=8,-1,0
  4541.8    0.05       0  4576.7    0.12       0  4739.5    0.05       0
  4783.1    0.05       0  4787.1    0.05       0  5089.5     0.1       0
  5186.6    0.05       0  5200.6     0.1       0
Bank Sta=4783.1,4787.1
Exp/Cntr=0.3,0.1

Type RM Length L Ch R = 1,16668,452,452,452
BEGIN DESCRIPTION:
TANTROUGH CREEK 32.0
END DESCRIPTION:
XS GIS Cut Line= 3
      2884455.69     10234553.07      2884400.50     10234778.00
      2884055.66     10235353.15
#Sta/Elev= 30
  4768.4 1005.96  4791.8 1005.73  4819.9 1003.43  4881.7  995.86  4922.9  994.15
  4997.6  993.67  4997.9  990.67  5001.4  990.67  5001.6  993.67  5015.4  994.03
  5021.3  995.80  5036.8  995.71  5042.7  996.83  5052.4  995.71  5058.2  997.15
  5073.8  997.18  5087.6  998.76  5174.8  999.08  5227.3 1000.88  5262.5 1000.16
  5349.8 1001.39  5386.7 1002.83  5524.8 1004.18  5607.0 1006.72  5614.9 1006.84
  5641.4 1008.23  5657.0 1010.42  5662.8 1009.84  5667.6 1011.98  5670.6 1011.98
#Mann=5,-1,0
  4768.4    0.05       0  4997.6    0.05       0  5001.6    0.05       0
  5607.0   0.075       0  5614.9    0.05       0
Bank Sta=4997.6,5001.6
Exp/Cntr=0.3,0.1

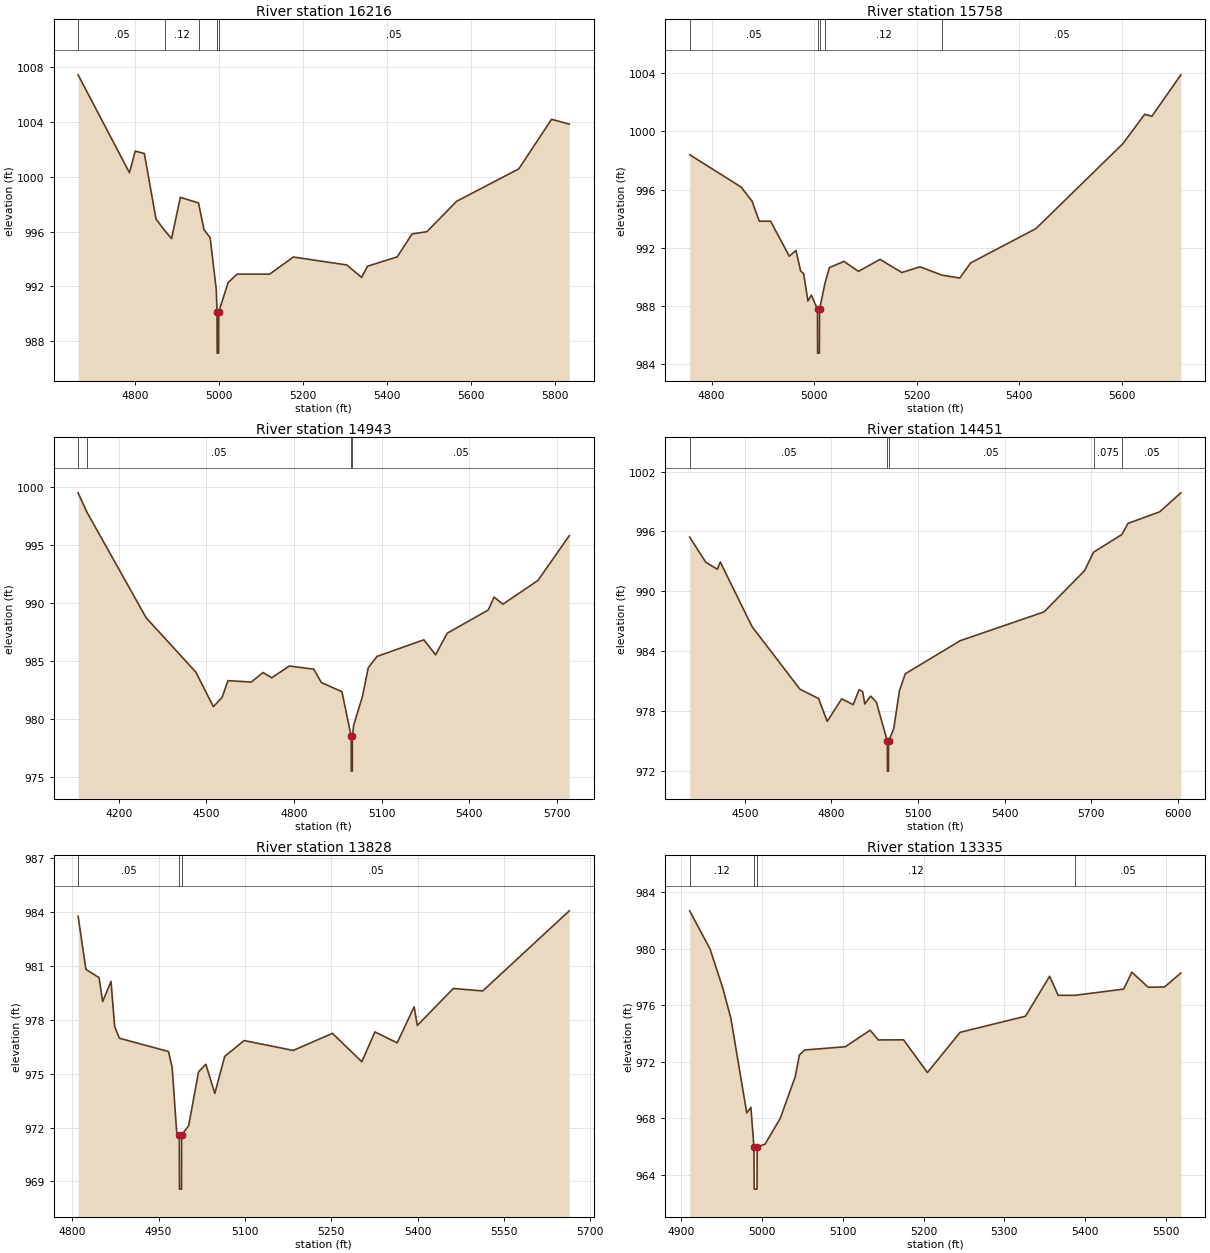
Type RM Length L Ch R = 1,16216,458,458,458
BEGIN DESCRIPTION:
TANTROUGH CREEK 31.0
END DESCRIPTION:
XS GIS Cut Line= 3
      2884355.68     10234303.12      2884084.50     10234501.00
      2883505.69     10235103.11
#Sta/Elev= 30
  4664.3 1007.46  4786.7 1000.31  4800.5 1001.89  4822.2 1001.71  4850.0  996.93
  4871.9  996.04  4887.1  995.50  4908.0  998.51  4951.4  998.10  4964.4  996.15
  4979.1  995.56  4993.7  991.78  4995.5  990.13  4995.8  987.13  4999.3  987.13
  4999.5  990.13  5021.8  992.28  5043.2  992.90  5120.9  992.90  5177.5  994.15
  5304.8  993.57  5340.1  992.66  5354.2  993.48  5425.0  994.16  5460.5  995.84
  5495.7  996.00  5566.5  998.22  5714.9 1000.59  5792.9 1004.21  5835.2 1003.86
#Mann=5,-1,0
  4664.3    0.05       0  4871.9    0.12       0  4951.4    0.05       0
  4995.5    0.05       0  4999.5    0.05       0
Bank Sta=4995.5,4999.5
Exp/Cntr=0.3,0.1

Type RM Length L Ch R = 1,15758,815,815,815
BEGIN DESCRIPTION:
TANTROUGH CREEK 30.0
END DESCRIPTION:
XS GIS Cut Line= 3
      2883905.71     10234153.10      2883705.75     10234291.00
      2883205.66     10234803.13
#Sta/Elev= 30
  4757.1  998.39  4857.2  996.18  4878.6  995.22  4893.0  993.83  4915.0  993.83
  4951.5  991.43  4964.7  991.82  4973.5  990.43  4979.6  990.22  4987.9  988.35
  4994.5  988.76  5006.6  987.78  5006.8  984.78  5010.3  984.78  5010.6  987.78
  5021.1  989.56  5029.9  990.65  5058.2  991.07  5086.5  990.39  5128.7  991.21
  5171.2  990.31  5206.6  990.70  5249.6  990.13  5284.3  989.93  5305.6  990.97
  5432.9  993.32  5602.7  999.15  5645.1 1001.16  5659.3 1001.03  5715.8 1003.87
#Mann=5,-1,0
  4757.1    0.05       0  5006.6    0.05       0  5010.6    0.05       0
  5021.1    0.12       0  5249.6    0.05       0
Bank Sta=5006.6,5010.6
Exp/Cntr=0.3,0.1

Type RM Length L Ch R = 1,14943,492,492,492
BEGIN DESCRIPTION:
Mapping XS 16362f79
END DESCRIPTION:
XS GIS Cut Line= 3
      2883223.11     10232880.20      2883223.11     10233686.69
      2883274.48     10234560.00
#Sta/Elev= 30
  4061.0  999.49  4091.3  997.82  4293.9  988.72  4463.9  984.04  4523.9  981.06
  4553.9  981.85  4573.9  983.30  4653.9  983.18  4693.9  984.00  4723.9  983.55
  4783.9  984.56  4867.5  984.29  4894.0  983.13  4964.1  982.35  4995.8  978.50
  4996.1  975.50  4999.6  975.50  4999.8  978.50  5004.1  979.45  5034.2  981.92
  5054.2  984.41  5084.3  985.39  5244.6  986.82  5284.6  985.53  5324.7  987.39
  5464.9  989.39  5485.0  990.50  5515.0  989.89  5635.2  991.94  5742.3  995.80
#Mann=4,-1,0
  4061.0    0.12       0  4091.3    0.05       0  4995.8    0.05       0
  4999.8    0.05       0
Bank Sta=4995.8,4999.8
Exp/Cntr=0.3,0.1

Type RM Length L Ch R = 1,14451,623,623,623
BEGIN DESCRIPTION:
Mapping XS fb1cd772
END DESCRIPTION:
XS GIS Cut Line= 3
      2882862.77     10232777.30      2882914.25     10233875.44
      2882879.93     10234476.01
#Sta/Elev= 30
  4309.0  995.43  4364.9  992.90  4404.9  992.20  4414.9  992.93  4525.1  986.44
  4690.9  980.16  4755.3  979.23  4785.3  976.93  4835.4  979.19  4875.4  978.61
  4895.5  980.11  4907.8  979.94  4915.5  978.68  4935.5  979.47  4955.5  978.87
  4993.6  974.94  4993.8  971.94  4997.3  971.94  4997.6  974.94  5015.6  976.19
  5035.6  980.03  5055.6  981.71  5245.8  985.03  5536.2  987.92  5676.5  992.06
  5707.4  993.91  5805.5  995.68  5826.7  996.80  5936.9  997.97  6009.9  999.87
#Mann=5,-1,0
  4309.0    0.05       0  4993.6    0.05       0  4997.6    0.05       0
  5707.4   0.075       0  5805.5    0.05       0
Bank Sta=4993.6,4997.6
Exp/Cntr=0.3,0.1

Type RM Length L Ch R = 1,13828,493,493,493
BEGIN DESCRIPTION:
TANTROUGH CREEK 26.0
END DESCRIPTION:
XS GIS Cut Line= 3
      2882555.70     10232953.09      2882440.75     10233104.00
      2882155.67     10233703.14
#Sta/Elev= 30
  4810.3  983.76  4823.9  980.80  4846.7  980.34  4853.0  979.01  4867.5  980.13
  4873.8  977.61  4882.0  976.97  4967.3  976.23  4973.7  975.34  4981.8  971.63
  4986.1  971.57  4986.4  968.57  4989.9  968.57  4990.1  971.57  5002.4  972.11
  5019.5  975.10  5032.2  975.52  5047.8  973.90  5065.0  975.96  5098.7  976.84
  5184.0  976.29  5252.2  977.24  5303.1  975.66  5325.9  977.32  5364.5  976.71
  5394.0  978.72  5399.5  977.68  5462.1  979.74  5513.1  979.60  5663.5  984.06
#Mann=3,-1,0
  4810.3    0.05       0  4986.1    0.05       0  4990.1    0.05       0
Bank Sta=4986.1,4990.1
Exp/Cntr=0.3,0.1

Type RM Length L Ch R = 1,13335,417,417,417
BEGIN DESCRIPTION:
TANTROUGH CREEK 25.0
END DESCRIPTION:
XS GIS Cut Line= 3
      2882105.68     10232753.11      2882087.75     10232841.00
      2882005.69     10233353.07
#Sta/Elev= 30
  4910.3  982.70  4935.6  979.99  4951.1  977.27  4961.3  975.10  4981.0  968.39
  4986.1  968.79  4989.9  966.00  4990.2  963.00  4993.7  963.00  4993.9  966.00
  5003.6  966.18  5022.4  968.00  5041.1  970.97  5046.2  972.50  5052.8  972.85
  5103.1  973.08  5133.8  974.25  5143.9  973.56  5175.2  973.57  5204.7  971.25
  5245.2  974.10  5326.2  975.24  5356.1  978.07  5366.7  976.72  5387.6  976.72
  5447.8  977.16  5457.9  978.36  5478.1  977.29  5498.4  977.31  5518.6  978.30
#Mann=4,-1,0
  4910.3    0.12       0  4989.9    0.07       0  4993.9    0.12       0
  5387.6    0.05       0
Bank Sta=4989.9,4993.9
Exp/Cntr=0.3,0.1

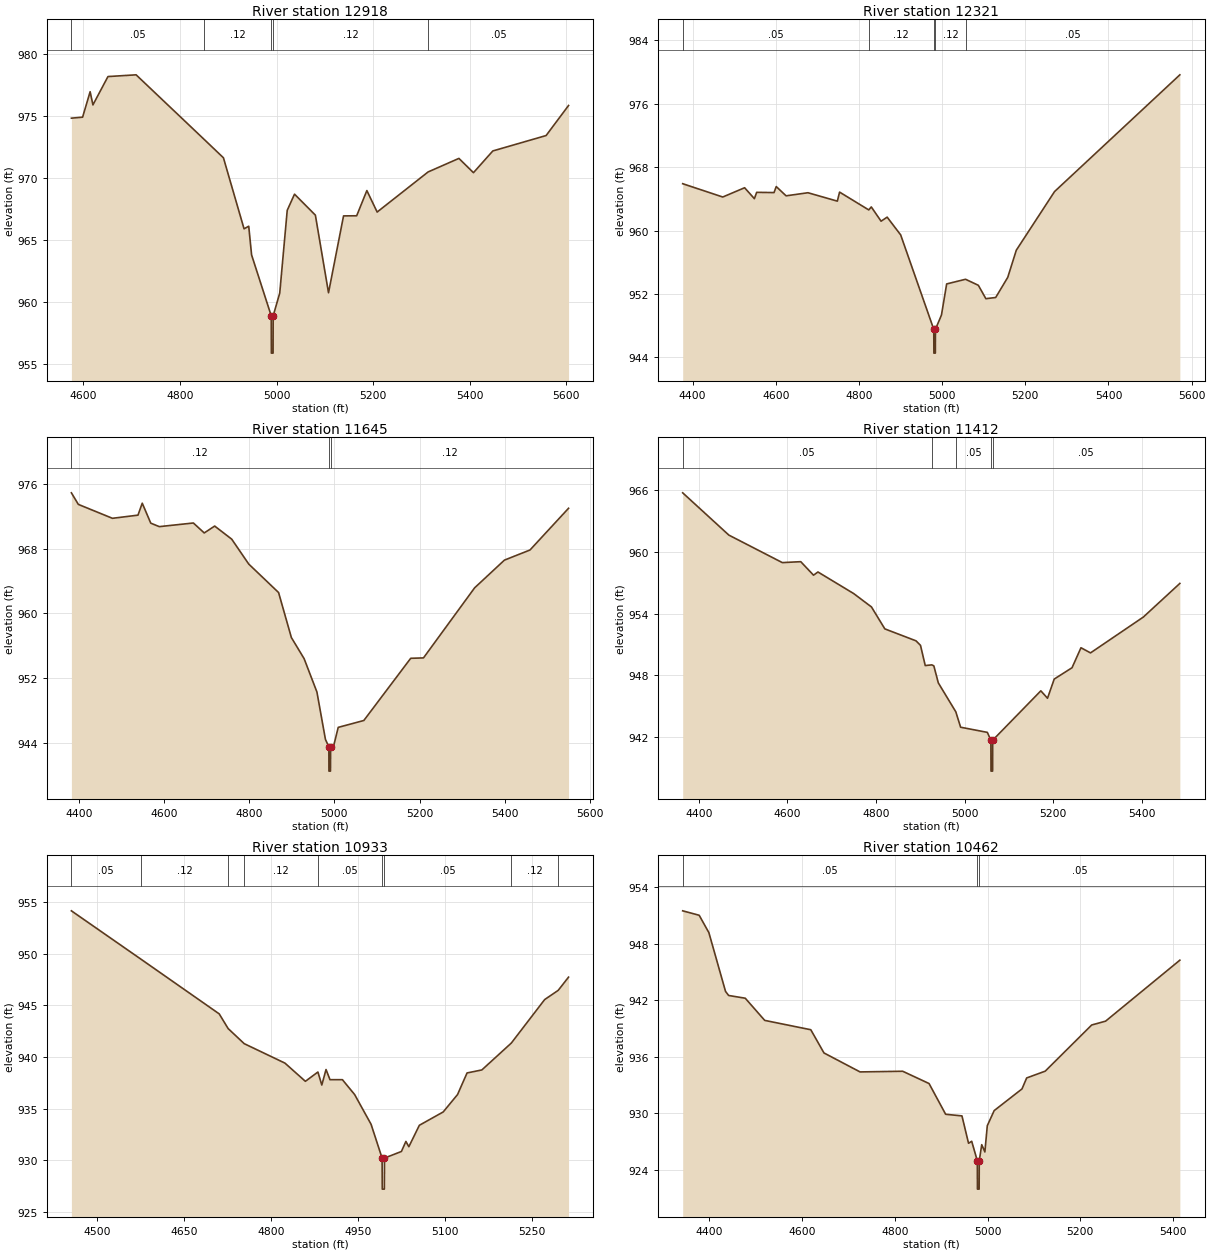
Type RM Length L Ch R = 1,12918,597,597,597
BEGIN DESCRIPTION:
Mapping XS 6376fb0a
END DESCRIPTION:
XS GIS Cut Line= 3
      2881901.86     10232416.94      2881593.01     10232931.69
      2881558.79     10233359.43
#Sta/Elev= 30
  4575.1  974.83  4598.3  974.91  4613.9  976.96  4619.7  975.90  4650.8  978.18
  4709.1  978.32  4848.9  973.16  4889.9  971.64  4932.6  965.92  4942.3  966.13
  4948.2  963.82  4988.9  958.91  4989.2  955.91  4992.7  955.91  4992.9  958.91
  5006.5  960.75  5022.0  967.41  5037.1  968.71  5080.3  967.02  5107.5  960.77
  5138.6  966.96  5165.8  966.97  5186.9  969.00  5208.2  967.27  5313.7  970.50
  5377.5  971.59  5407.6  970.44  5447.7  972.19  5558.0  973.43  5604.5  975.85
#Mann=5,-1,0
  4575.1    0.05       0  4848.9    0.12       0  4988.9    0.07       0
  4992.9    0.12       0  5313.7    0.05       0
Bank Sta=4988.9,4992.9
Exp/Cntr=0.3,0.1

Type RM Length L Ch R = 1,12321,676,676,676
BEGIN DESCRIPTION:
Mapping XS 517f40fc
END DESCRIPTION:
XS GIS Cut Line= 3
      2881987.66     10232159.54      2881266.99     10232468.40
      2880959.41     10232741.81
#Sta/Elev= 30
  4376.1  965.91  4472.4  964.23  4525.0  965.40  4548.5  964.02  4554.0  964.82
  4595.7  964.79  4601.1  965.55  4624.7  964.38  4677.3  964.77  4748.0  963.71
  4753.4  964.85  4823.6  962.60  4829.6  962.98  4853.2  961.18  4867.8  961.69
  4900.3  959.45  4979.9  947.53  4980.2  944.53  4983.7  944.53  4983.9  947.53
  4998.4  949.34  5010.9  953.26  5056.3  953.85  5087.1  953.09  5105.2  951.40
  5128.8  951.55  5157.8  954.09  5178.4  957.52  5270.4  964.92  5571.7  979.65
#Mann=5,-1,0
  4376.1    0.05       0  4823.6    0.12       0  4979.9    0.07       0
  4983.9    0.12       0  5056.3    0.05       0
Bank Sta=4979.9,4983.9
Exp/Cntr=0.3,0.1

Type RM Length L Ch R = 1,11645,233,233,233
BEGIN DESCRIPTION:
Mapping XS 65fa7d69
END DESCRIPTION:
XS GIS Cut Line= 2
      2882021.97     10231833.52      2880855.19     10231850.68
#Sta/Elev= 30
  4382.7  974.91  4399.0  973.48  4479.0  971.76  4539.0  972.15  4549.0  973.63
  4569.0  971.16  4589.0  970.73  4669.0  971.18  4694.5  969.95  4719.0  970.80
  4759.0  969.18  4799.0  966.10  4869.0  962.58  4899.0  957.02  4929.0  954.40
  4959.0  950.28  4979.0  944.42  4987.0  943.50  4987.2  940.50  4990.8  940.50
  4991.1  943.50  4999.0  943.78  5009.0  945.91  5069.1  946.76  5179.1  954.45
  5209.1  954.50  5329.1  963.16  5399.1  966.59  5459.1  967.84  5549.6  973.00
#Mann=3,-1,0
  4382.7    0.12       0  4987.0    0.07       0  4991.1    0.12       0
Bank Sta=4987,4991.1
Exp/Cntr=0.3,0.1

Type RM Length L Ch R = 1,11412,479,479,479
BEGIN DESCRIPTION:
Mapping XS 34317b4f
END DESCRIPTION:
XS GIS Cut Line= 2
      2882039.17     10231696.25      2880923.82     10231576.14
#Sta/Elev= 30
  4363.7  965.72  4467.8  961.62  4588.5  958.95  4630.1  959.04  4658.9  957.73
  4668.9  958.04  4749.4  955.95  4789.6  954.65  4819.8  952.52  4890.2  951.36
  4900.3  950.92  4911.0  948.96  4925.8  949.03  4930.4  948.93  4940.5  947.28
  4980.0  944.47  4990.8  942.98  5051.1  942.48  5059.1  941.72  5059.4  938.72
  5063.0  938.72  5063.2  941.72  5171.8  946.51  5186.9  945.79  5202.0  947.65
  5242.2  948.75  5262.4  950.69  5283.9  950.19  5403.2  953.67  5485.5  956.93
#Mann=5,-1,0
  4363.7    0.05       0  4925.8    0.12       0  4980.0    0.05       0
  5059.1    0.03       0  5063.2    0.05       0
Bank Sta=5059.1,5063.2
Exp/Cntr=0.3,0.1

Type RM Length L Ch R = 1,10933,471,471,471
BEGIN DESCRIPTION:
TANTROUGH CREEK 20.0
END DESCRIPTION:
XS GIS Cut Line= 3
      2881805.67     10231553.10      2881409.50     10231180.00
      2881105.67     10231253.11
#Sta/Elev= 30
  4455.8  954.13  4575.8  949.45  4710.5  944.17  4725.9  942.75  4753.6  941.29
  4823.8  939.41  4859.0  937.65  4880.6  938.55  4887.3  937.29  4894.6  938.79
  4901.4  937.81  4922.8  937.81  4943.9  936.37  4972.2  933.50  4991.2  930.23
  4991.5  927.23  4995.1  927.23  4995.3  930.23  5024.5  930.87  5032.2  931.84
  5037.3  931.33  5055.4  933.40  5096.5  934.69  5121.2  936.37  5137.6  938.46
  5163.1  938.75  5213.9  941.35  5271.3  945.55  5294.6  946.44  5312.5  947.72
#Mann=9,-1,0
  4455.8    0.05       0  4575.8    0.12       0  4725.9    0.05       0
  4753.6    0.12       0  4880.6    0.05       0  4991.2    0.05       0
  4995.3    0.05       0  5213.9    0.12       0  5294.6    0.05       0
Bank Sta=4991.2,4995.3
Exp/Cntr=0.3,0.1

Type RM Length L Ch R = 1,10462,307,307,307
BEGIN DESCRIPTION:
TANTROUGH CREEK 19.0
END DESCRIPTION:
XS GIS Cut Line= 3
      2881905.70     10231153.13      2881420.00     10230711.00
      2881005.68     10230703.11
#Sta/Elev= 30
  4343.2  951.47  4378.7  951.00  4399.6  949.16  4435.5  942.93  4442.2  942.50
  4478.0  942.21  4519.9  939.86  4619.2  938.87  4647.6  936.41  4725.3  934.40
  4817.2  934.47  4874.0  933.17  4909.8  929.91  4944.9  929.74  4959.1  926.84
  4965.9  927.05  4978.0  924.98  4978.3  921.98  4981.9  921.98  4982.2  924.98
  4987.5  926.69  4994.3  925.92  4999.5  928.70  5014.3  930.30  5074.3  932.60
  5084.3  933.76  5124.3  934.48  5224.4  939.37  5254.4  939.78  5414.4  946.24
#Mann=3,-1,0
  4343.2    0.05       0  4978.0    0.05       0  4982.2    0.05       0
Bank Sta=4978,4982.2
Exp/Cntr=0.3,0.1

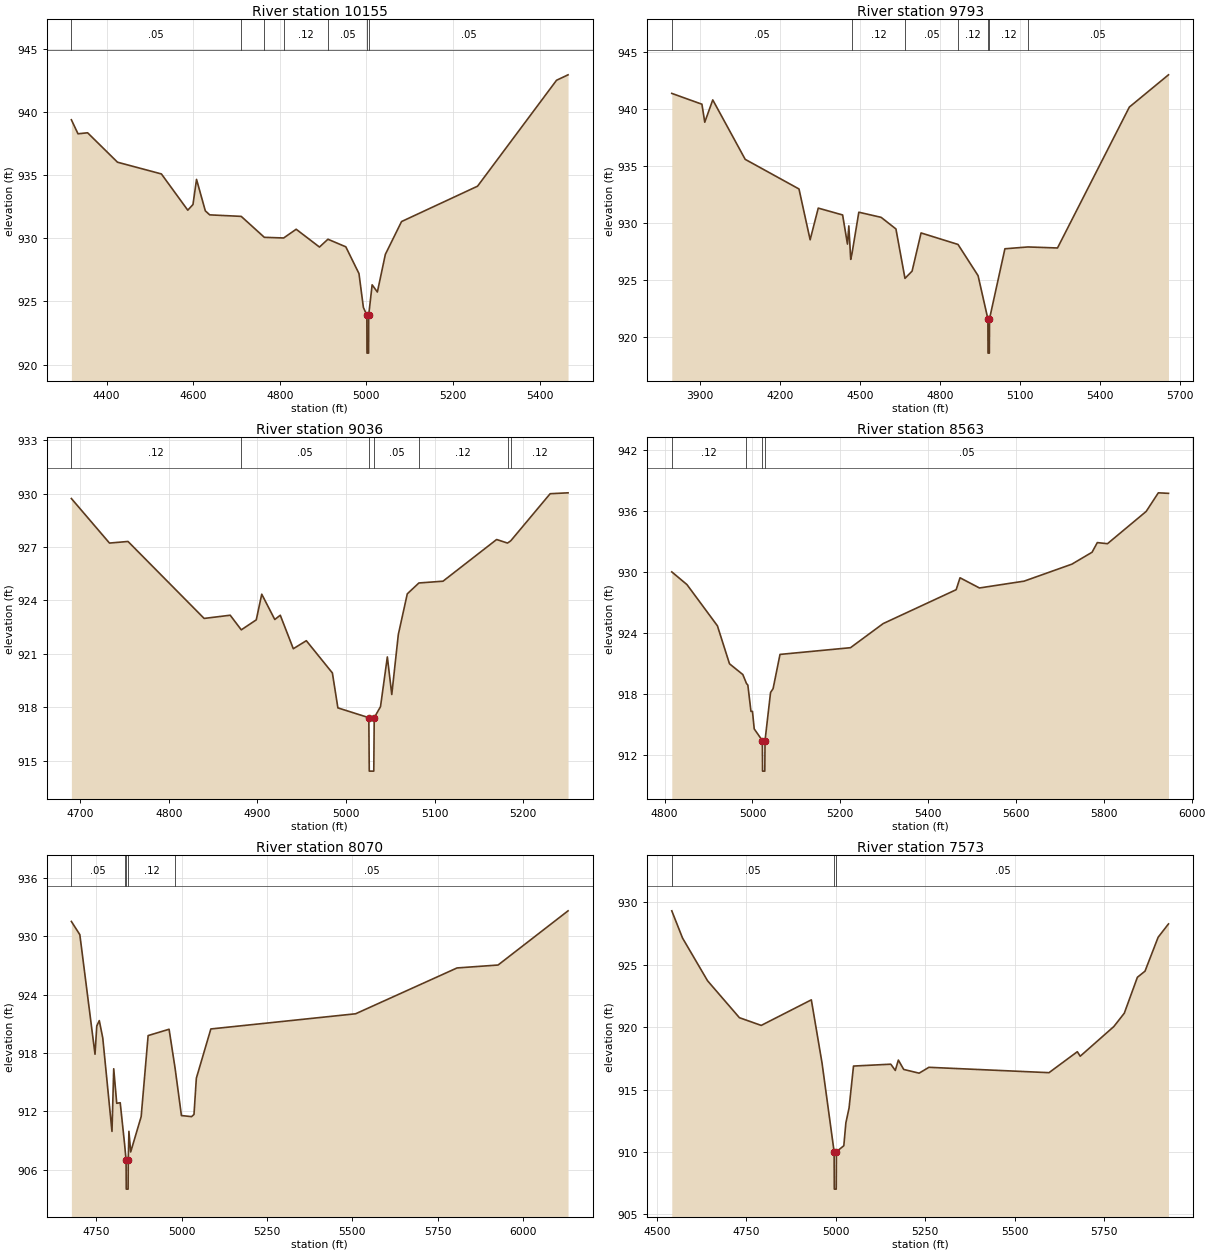
Type RM Length L Ch R = 1,10155,362,362,362
BEGIN DESCRIPTION:
Mapping XS f5c5e12d
END DESCRIPTION:
XS GIS Cut Line= 2
      2882210.78     10230563.76      2881079.48     10230375.22
#Sta/Elev= 30
  4318.7  939.39  4334.0  938.28  4356.2  938.36  4425.2  936.03  4526.6  935.10
  4587.5  932.23  4599.5  932.68  4607.7  934.67  4628.0  932.18  4638.1  931.86
  4710.9  931.74  4764.3  930.08  4808.9  930.03  4837.8  930.72  4891.6  929.31
  4911.1  929.93  4952.4  929.33  4982.8  927.21  4993.0  924.53  5001.0  923.91
  5001.3  920.91  5005.0  920.91  5005.2  923.91  5013.2  926.32  5025.3  925.75
  5043.7  928.73  5081.1  931.33  5256.6  934.13  5439.0  942.52  5465.6  942.95
#Mann=7,-1,0
  4318.7    0.05       0  4710.9    0.12       0  4764.3    0.05       0
  4808.9    0.12       0  4911.1    0.05       0  5001.0    0.05       0
  5005.2    0.05       0
Bank Sta=5001,5005.2
Exp/Cntr=0.3,0.1

Type RM Length L Ch R = 1,9793,757,757,757
BEGIN DESCRIPTION:
Mapping XS a9753dff
END DESCRIPTION:
XS GIS Cut Line= 2
      2882897.12     10230357.85      2881061.11     10230048.99
#Sta/Elev= 30
  3795.1  941.41  3908.1  940.46  3918.7  938.88  3948.7  940.84  4070.3  935.62
  4271.9  933.02  4313.7  928.56  4344.1  931.34  4435.4  930.74  4453.6  928.18
  4458.7  929.78  4465.8  926.84  4470.3  927.31  4496.2  930.98  4579.8  930.53
  4635.3  929.51  4669.2  925.17  4695.9  925.81  4729.5  929.16  4868.0  928.15
  4943.2  925.41  4980.0  921.61  4980.5  918.61  4985.5  918.61  4986.0  921.61
  5043.8  927.77  5130.2  927.93  5240.9  927.84  5510.3  940.21  5656.9  943.04
#Mann=7,-1,0
  3795.1    0.05       0  4470.3    0.12       0  4669.2    0.05       0
  4868.0    0.12       0  4980.0    0.07       0  4986.0    0.12       0
  5130.2    0.05       0
Bank Sta=4980,4986
Exp/Cntr=0.3,0.1

Type RM Length L Ch R = 1,9036,473,473,473
BEGIN DESCRIPTION:
TANTROUGH CREEK 16.0
END DESCRIPTION:
XS GIS Cut Line= 3
      2881905.71     10229653.13      2881654.25     10229472.00
      2881405.69     10229503.11
#Sta/Elev= 30
  4690.1  929.72  4733.1  927.22  4754.0  927.31  4839.9  922.99  4869.3  923.17
  4881.8  922.35  4898.7  922.91  4904.9  924.35  4919.6  922.93  4925.8  923.17
  4940.5  921.29  4955.2  921.74  4984.6  919.93  4990.8  917.97  5025.7  917.42
  5026.2  914.42  5031.3  914.42  5031.8  917.42  5038.9  918.04  5046.6  920.83
  5051.6  918.72  5059.0  922.09  5069.1  924.37  5082.2  924.98  5109.4  925.08
  5169.9  927.42  5182.2  927.22  5185.9  927.35  5230.3  929.99  5250.5  930.04
#Mann=7,-1,0
  4690.1    0.12       0  4881.8    0.05       0  5025.7    0.05       0
  5031.8    0.05       0  5082.2    0.12       0  5182.2    0.05       0
  5185.9    0.12       0
Bank Sta=5025.7,5031.8
Exp/Cntr=0.3,0.1

Type RM Length L Ch R = 1,8563,493,493,493
BEGIN DESCRIPTION:
TANTROUGH CREEK 15.0
END DESCRIPTION:
XS GIS Cut Line= 3
      2881955.69     10229103.11      2881774.00     10229076.00
      2880955.72     10229553.09
#Sta/Elev= 30
  4816.3  930.02  4850.9  928.77  4920.2  924.72  4947.7  920.99  4978.1  919.93
  4986.3  919.06  4989.5  918.89  4996.6  916.31  5000.0  916.31  5004.0  914.59
  5022.5  913.44  5023.0  910.44  5028.1  910.44  5028.6  913.44  5041.2  918.17
  5047.0  918.55  5062.7  921.91  5223.2  922.57  5297.6  924.94  5463.8  928.27
  5472.6  929.44  5516.8  928.44  5618.5  929.11  5727.3  930.78  5773.2  931.95
  5785.2  932.90  5808.3  932.79  5896.4  935.96  5924.1  937.79  5947.2  937.74
#Mann=4,-1,0
  4816.3    0.12       0  4986.3    0.05       0  5022.5    0.05       0
  5028.6    0.05       0
Bank Sta=5022.5,5028.6
Exp/Cntr=0.3,0.1

Type RM Length L Ch R = 1,8070,497,497,497
BEGIN DESCRIPTION:
TANTROUGH CREEK 14.0
END DESCRIPTION:
XS GIS Cut Line= 3
      2882105.70     10228653.12      2881789.75     10228586.00
      2881005.72     10229403.08
#Sta/Elev= 30
  4677.0  931.52  4701.8  930.16  4746.3  917.87  4751.4  920.78  4758.8  921.33
  4769.0  919.54  4796.0  909.94  4801.1  916.38  4809.9  912.83  4820.1  912.89
  4832.9  908.65  4837.3  907.01  4837.8  904.01  4843.2  904.01  4843.7  907.01
  4845.6  909.95  4850.8  907.83  4881.5  911.46  4901.9  919.79  4963.3  920.44
  4980.8  916.46  4999.5  911.57  5029.1  911.46  5036.3  911.68  5043.2  915.41
  5085.7  920.47  5509.9  922.03  5807.1  926.74  5927.3  927.04  6132.4  932.61
#Mann=5,-1,0
  4677.0    0.05       0  4832.9    0.12       0  4837.3    0.05       0
  4843.7    0.12       0  4980.8    0.05       0
Bank Sta=4837.3,4843.7
Exp/Cntr=0.3,0.1

Type RM Length L Ch R = 1,7573,498,498,498
BEGIN DESCRIPTION:
TANTROUGH CREEK 13.0
END DESCRIPTION:
XS GIS Cut Line= 3
      2882055.65     10228153.11      2881597.00     10228165.00
      2880805.73     10228653.09
#Sta/Elev= 30
  4541.2  929.33  4571.2  927.15  4641.2  923.72  4730.2  920.76  4791.2  920.14
  4931.3  922.19  4961.3  917.11  4995.0  910.01  4995.5  907.01  5000.9  907.01
  5001.4  910.01  5022.1  910.49  5027.9  912.33  5036.8  913.52  5049.2  916.88
  5153.4  917.03  5166.0  916.53  5174.6  917.36  5189.5  916.61  5232.6  916.31
  5260.0  916.78  5595.7  916.35  5674.9  918.03  5683.0  917.67  5777.0  920.05
  5806.2  921.12  5842.8  924.00  5864.1  924.49  5900.8  927.21  5929.7  928.28
#Mann=3,-1,0
  4541.2    0.05       0  4995.0    0.05       0  5001.4    0.05       0
Bank Sta=4995,5001.4
Exp/Cntr=0.3,0.1

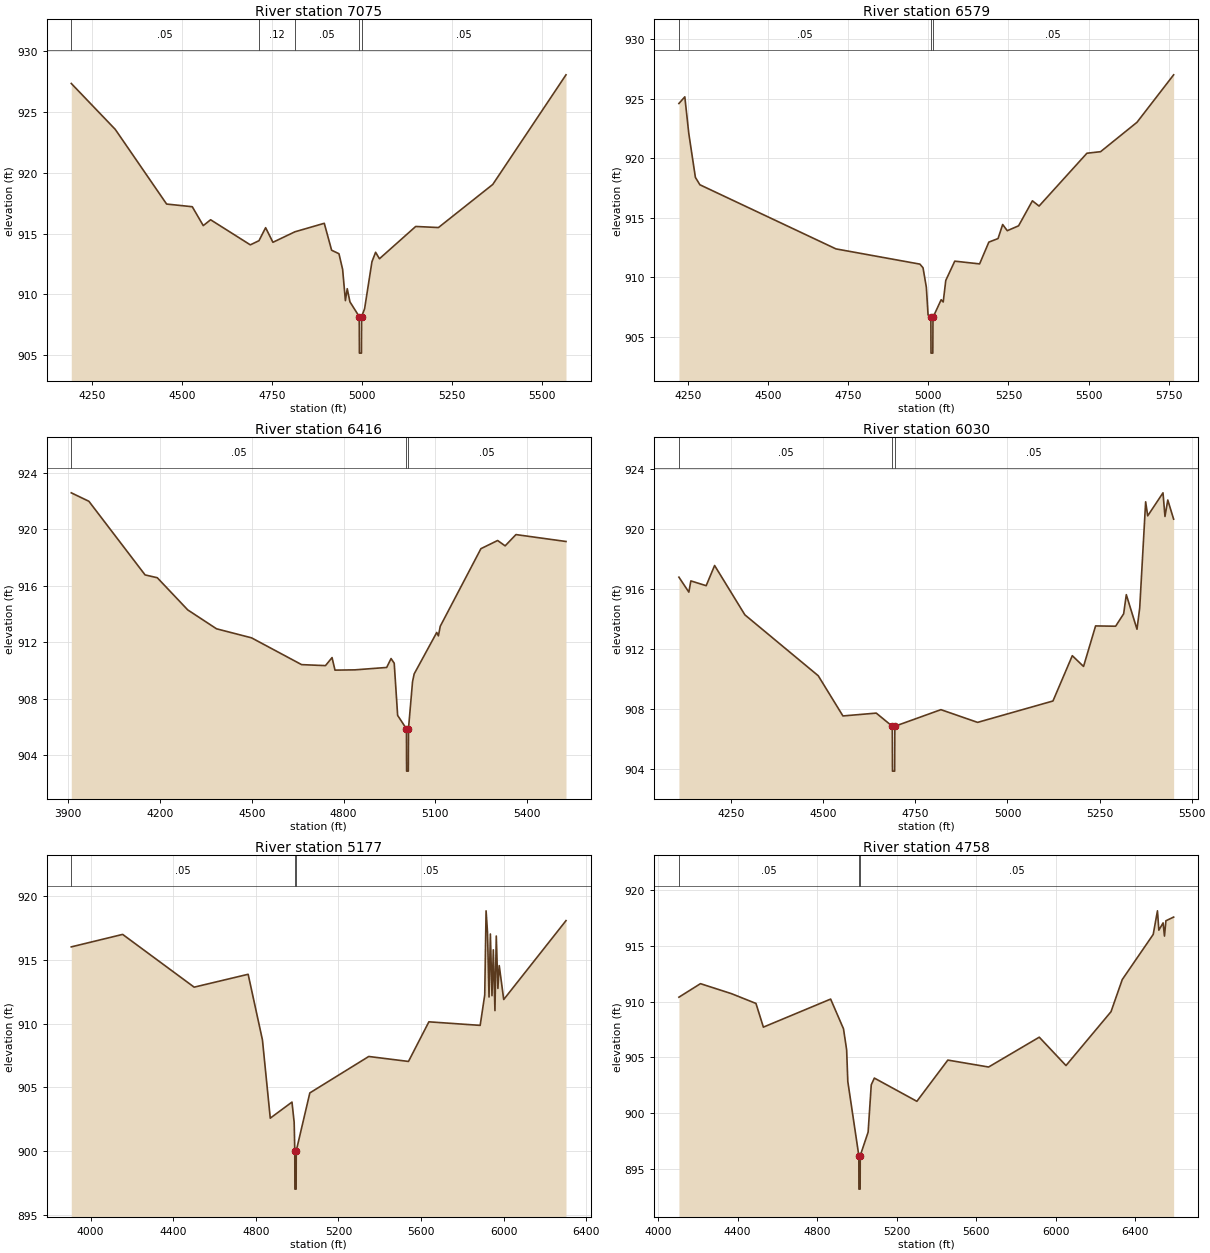
Type RM Length L Ch R = 1,7075,496,496,496
BEGIN DESCRIPTION:
TANTROUGH CREEK 12.0
END DESCRIPTION:
XS GIS Cut Line= 3
      2882055.64     10227953.10      2881263.50     10227800.00
      2880705.65     10227903.12
#Sta/Elev= 30
  4193.2  927.32  4315.4  923.55  4458.0  917.42  4529.3  917.20  4559.8  915.65
  4580.2  916.13  4690.5  914.07  4714.5  914.41  4733.0  915.48  4753.3  914.28
  4814.2  915.14  4895.9  915.84  4916.3  913.63  4936.7  913.34  4946.9  912.05
  4954.6  909.49  4959.7  910.47  4967.2  909.39  4993.0  908.18  4993.5  905.18
  4999.1  905.18  4999.6  908.18  5007.9  908.82  5028.3  912.68  5038.5  913.46
  5049.2  912.93  5149.9  915.58  5213.0  915.49  5363.9  919.03  5567.3  928.03
#Mann=5,-1,0
  4193.2    0.05       0  4714.5    0.12       0  4814.2    0.05       0
  4993.0    0.05       0  4999.6    0.05       0
Bank Sta=4993,4999.6
Exp/Cntr=0.3,0.1

Type RM Length L Ch R = 1,6579,163,163,163
BEGIN DESCRIPTION:
TANTROUGH CREEK 11.0
END DESCRIPTION:
XS GIS Cut Line= 3
      2882055.67     10227503.11      2881300.00     10227321.00
      2880705.66     10227803.13
#Sta/Elev= 30
  4222.7  924.61  4241.1  925.17  4253.5  922.09  4274.1  918.40  4288.1  917.78
  4712.4  912.39  4974.2  911.11  4983.9  910.80  4994.2  909.17  4999.6  906.84
  5008.3  906.63  5008.8  903.63  5014.4  903.63  5014.9  906.63  5040.4  908.12
  5046.8  907.93  5054.8  909.74  5082.8  911.36  5160.3  911.13  5189.1  912.96
  5217.8  913.26  5232.2  914.44  5246.6  913.92  5281.8  914.33  5324.9  916.43
  5345.7  915.99  5494.9  920.43  5537.5  920.56  5651.0  923.03  5765.3  927.02
#Mann=3,-1,0
  4222.7    0.05       0  5008.3    0.05       0  5014.9    0.05       0
Bank Sta=5008.3,5014.9
Exp/Cntr=0.3,0.1

Type RM Length L Ch R = 1,6416,386,386,386
BEGIN DESCRIPTION:
Mapping XS 3d5fa20c
END DESCRIPTION:
XS GIS Cut Line= 2
      2882210.76     10226805.93      2880702.34     10227388.73
#Sta/Elev= 30
  3909.7  922.59  3967.3  921.99  4151.0  916.77  4190.9  916.57  4290.4  914.29
  4384.5  912.95  4498.9  912.31  4662.6  910.41  4740.6  910.34  4762.1  910.91
  4771.7  910.02  4837.1  910.04  4940.7  910.21  4955.0  910.84  4965.3  910.51
  4976.5  906.81  5005.3  905.86  5005.8  902.86  5011.4  902.86  5011.9  905.86
  5025.2  909.20  5030.5  909.75  5104.3  912.69  5109.7  912.45  5115.8  913.13
  5248.7  918.63  5303.3  919.21  5327.9  918.83  5363.2  919.63  5526.8  919.14
#Mann=3,-1,0
  3909.7    0.05       0  5005.3    0.05       0  5011.9    0.05       0
Bank Sta=5005.3,5011.9
Exp/Cntr=0.3,0.1

Type RM Length L Ch R = 1,6030,853,853,853
BEGIN DESCRIPTION:
Mapping XS d194814f
END DESCRIPTION:
XS GIS Cut Line= 2
      2881884.67     10226497.10      2880651.06     10227028.24
#Sta/Elev= 30
  4108.0  916.80  4135.0  915.80  4140.4  916.55  4182.0  916.23  4204.9  917.58
  4287.1  914.28  4486.2  910.21  4553.3  907.52  4643.7  907.71  4687.3  906.83
  4687.8  903.83  4693.7  903.83  4694.2  906.83  4819.3  907.94  4918.9  907.09
  5123.5  908.52  5176.0  911.55  5206.5  910.83  5239.2  913.54  5293.6  913.52
  5315.4  914.35  5322.6  915.63  5351.6  913.32  5359.0  914.74  5375.1  921.84
  5380.7  920.90  5422.2  922.44  5427.6  920.86  5435.2  921.96  5451.1  920.68
#Mann=3,-1,0
  4108.0    0.05       0  4687.3    0.03       0  4694.2    0.05       0
Bank Sta=4687.3,4694.2
Exp/Cntr=0.3,0.1

Type RM Length L Ch R = 1,5177,419,419,419
BEGIN DESCRIPTION:
Mapping XS 71450e9b
END DESCRIPTION:
XS GIS Cut Line= 3
      2882382.34     10225793.56      2881215.51     10226171.06
      2880460.59     10227063.25
#Sta/Elev= 30
  3906.3  916.03  4155.0  917.01  4501.2  912.87  4762.6  913.88  4831.8  908.73
  4869.7  902.59  4974.8  903.85  4985.4  902.26  4988.4  900.02  4988.9  897.02
  4994.9  897.02  4995.4  900.02  5061.2  904.57  5346.5  907.43  5538.8  907.04
  5637.6  910.15  5885.9  909.87  5908.0  912.26  5914.5  918.86  5921.3  917.19
  5928.8  912.10  5935.3  917.04  5943.1  912.20  5949.6  915.80  5957.4  911.03
  5963.9  916.88  5971.7  912.77  5978.2  914.56  5999.9  911.90  6301.4  918.09
#Mann=3,-1,0
  3906.3    0.05       0  4988.4    0.03       0  4995.4    0.05       0
Bank Sta=4988.4,4995.4
Exp/Cntr=0.3,0.1

Type RM Length L Ch R = 1,4758,1100,1100,1100
BEGIN DESCRIPTION:
Mapping XS 1dc242fb
END DESCRIPTION:
XS GIS Cut Line= 3
      2881987.67     10225295.96      2881061.08     10225827.88
      2880049.67     10226822.16
#Sta/Elev= 30
  4105.1  910.39  4213.4  911.60  4368.7  910.71  4492.4  909.83  4529.7  907.71
  4867.7  910.22  4932.4  907.56  4948.2  905.67  4954.0  902.85  5009.4  896.21
  5009.9  893.21  5016.0  893.21  5016.5  896.21  5056.1  898.31  5071.9  902.55
  5087.5  903.15  5301.2  901.07  5456.8  904.76  5661.8  904.14  5916.4  906.81
  6050.7  904.27  6277.0  909.09  6333.6  911.97  6489.2  916.01  6510.5  918.12
  6517.5  916.39  6538.8  917.04  6545.8  915.86  6552.9  917.23  6591.8  917.56
#Mann=3,-1,0
  4105.1    0.05       0  5009.4    0.03       0  5016.5    0.05       0
Bank Sta=5009.4,5016.5
Exp/Cntr=0.3,0.1