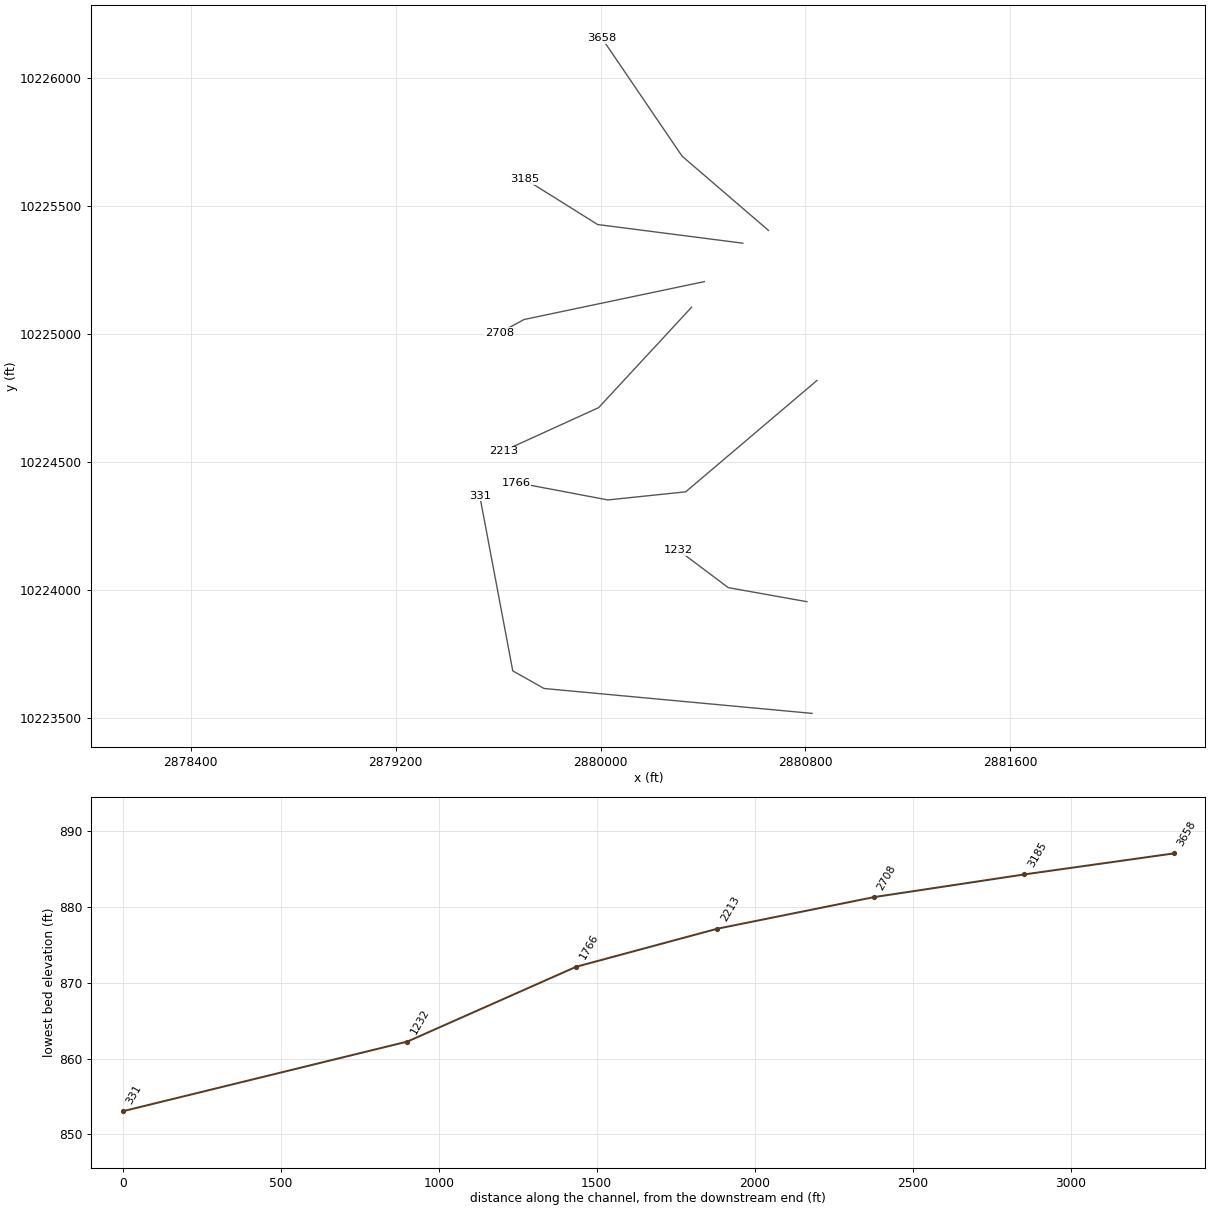
HEC-RAS study TANTROUGH CREEK.prj: TANTROUGH CREEK Base Level Engineering

--- TANTROUGH CREEK.g01 (geometry) --- (continued)

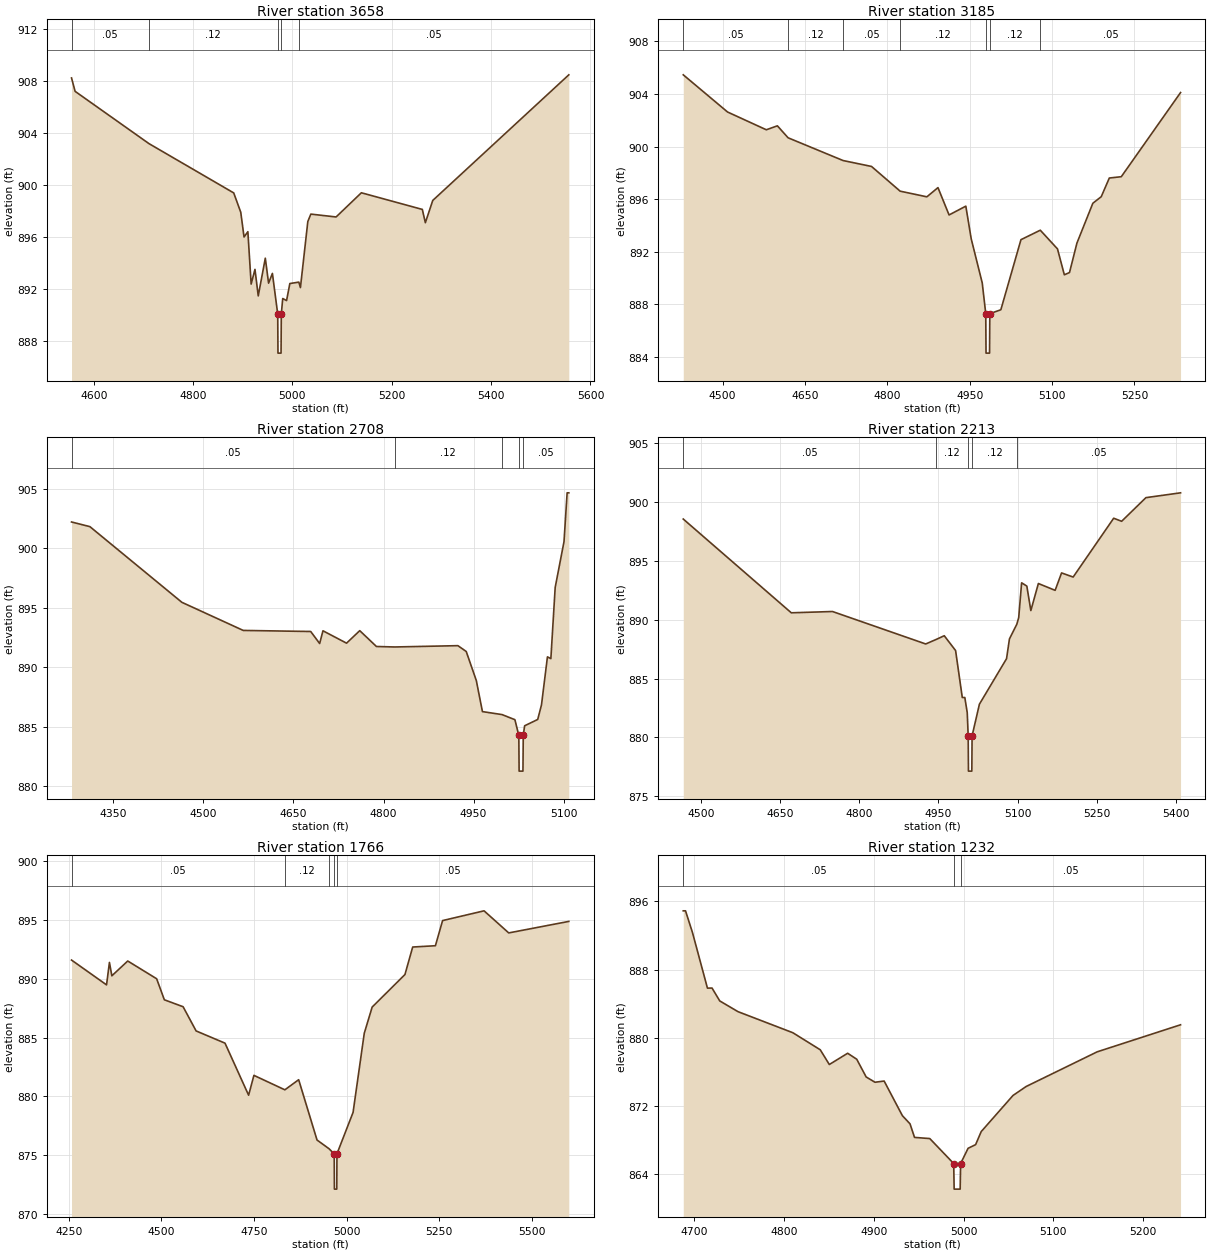
Type RM Length L Ch R = 1,3658,473,473,473
BEGIN DESCRIPTION:
TANTROUGH CREEK 7.0
END DESCRIPTION:
XS GIS Cut Line= 3
      2880655.71     10225403.09      2880318.50     10225693.00
      2880005.67     10226153.13
#Sta/Elev= 30
  4555.3  908.22  4562.5  907.19  4711.2  903.17  4881.8  899.38  4896.0  897.89
  4902.6  895.99  4910.3  896.40  4916.9  892.37  4924.6  893.50  4931.2  891.46
  4945.4  894.36  4952.0  892.44  4959.7  893.19  4970.4  890.06  4970.9  887.06
  4977.1  887.06  4977.6  890.06  4980.5  891.26  4988.2  891.10  4994.8  892.41
  5012.9  892.52  5016.1  892.10  5031.0  897.18  5037.1  897.75  5087.9  897.53
  5138.8  899.39  5261.5  898.11  5267.6  897.09  5282.5  898.80  5556.4  908.46
#Mann=5,-1,0
  4555.3    0.05       0  4711.2    0.12       0  4970.4    0.07       0
  4977.6    0.12       0  5012.9    0.05       0
Bank Sta=4970.4,4977.6
Exp/Cntr=0.3,0.1

Type RM Length L Ch R = 1,3185,477,477,477
BEGIN DESCRIPTION:
TANTROUGH CREEK 6.0
END DESCRIPTION:
XS GIS Cut Line= 3
      2880555.68     10225353.11      2879988.75     10225426.00
      2879705.69     10225603.11
#Sta/Elev= 30
  4428.4  905.46  4509.1  902.63  4579.6  901.28  4599.8  901.58  4619.3  900.67
  4719.4  898.94  4771.2  898.49  4823.3  896.61  4872.0  896.18  4892.2  896.88
  4912.4  894.80  4942.9  895.47  4952.7  892.99  4972.8  889.63  4979.2  887.29
  4979.7  884.29  4986.1  884.29  4986.6  887.29  5006.7  887.59  5043.3  892.92
  5078.5  893.64  5109.8  892.22  5122.3  890.25  5131.7  890.42  5145.2  892.66
  5174.2  895.69  5189.5  896.19  5204.2  897.61  5226.0  897.71  5333.9  904.11
#Mann=7,-1,0
  4428.4    0.05       0  4619.3    0.12       0  4719.4    0.05       0
  4823.3    0.12       0  4979.2    0.07       0  4986.6    0.12       0
  5078.5    0.05       0
Bank Sta=4979.2,4986.6
Exp/Cntr=0.3,0.1

Type RM Length L Ch R = 1,2708,495,495,495
BEGIN DESCRIPTION:
TANTROUGH CREEK 5.0
END DESCRIPTION:
XS GIS Cut Line= 3
      2880405.65     10225203.10      2879701.25     10225055.00
      2879605.72     10225003.13
#Sta/Elev= 30
  4280.2  902.22  4310.8  901.83  4464.1  895.47  4566.3  893.11  4678.7  893.02
  4693.6  892.01  4699.1  893.08  4738.4  892.04  4760.4  893.09  4788.2  891.76
  4818.4  891.72  4923.9  891.83  4937.8  891.34  4954.6  888.90  4964.8  886.29
  4997.5  886.04  5018.9  885.61  5025.4  884.29  5025.9  881.29  5032.3  881.29
  5032.8  884.29  5035.1  885.10  5056.9  885.63  5063.2  886.86  5073.1  890.89
  5078.8  890.74  5086.0  896.72  5100.7  900.57  5105.9  904.67  5108.7  904.67
#Mann=5,-1,0
  4280.2    0.05       0  4818.4    0.12       0  4997.5    0.05       0
  5025.4    0.05       0  5032.8    0.05       0
Bank Sta=5025.4,5032.8
Exp/Cntr=0.3,0.1

Type RM Length L Ch R = 1,2213,447,447,447
BEGIN DESCRIPTION:
TANTROUGH CREEK 4.0
END DESCRIPTION:
XS GIS Cut Line= 3
      2880355.69     10225103.11      2879992.75     10224711.00
      2879620.23     10224541.19
#Sta/Elev= 30
  4465.7  898.56  4670.7  890.59  4748.9  890.70  4925.8  887.94  4945.4  888.32
  4961.0  888.64  4982.5  887.38  4995.2  883.39  5000.0  883.39  5004.6  882.10
  5006.4  880.13  5006.9  877.13  5013.3  877.13  5013.8  880.13  5027.7  882.82
  5079.2  886.69  5084.7  888.37  5098.7  889.62  5102.3  890.19  5107.8  893.14
  5117.7  892.86  5125.3  890.78  5139.6  893.08  5171.4  892.50  5183.6  893.98
  5205.6  893.63  5282.5  898.63  5297.6  898.37  5343.7  900.38  5409.4  900.79
#Mann=5,-1,0
  4465.7    0.05       0  4945.4    0.12       0  5006.4    0.07       0
  5013.8    0.12       0  5098.7    0.05       0
Bank Sta=5006.4,5013.8
Exp/Cntr=0.3,0.1

Type RM Length L Ch R = 1,1766,534,534,534
BEGIN DESCRIPTION:
Mapping XS ab631c92
END DESCRIPTION:
XS GIS Cut Line= 4
      2880845.36     10224817.07      2880332.60     10224382.08
      2880028.82     10224350.48      2879671.01     10224418.18
#Sta/Elev= 30
  4257.5  891.60  4352.0  889.49  4359.8  891.40  4366.3  890.26  4409.2  891.52
  4487.2  890.01  4508.0  888.22  4558.6  887.63  4593.7  885.57  4671.7  884.53
  4735.4  880.10  4749.7  881.79  4833.2  880.56  4870.5  881.42  4920.0  876.29
  4952.3  875.55  4966.4  875.11  4966.9  872.11  4973.3  872.11  4973.8  875.11
  5017.3  878.64  5047.5  885.37  5068.8  887.60  5157.3  890.37  5178.2  892.71
  5239.5  892.82  5258.9  894.96  5370.8  895.79  5437.4  893.91  5599.5  894.89
#Mann=5,-1,0
  4257.5    0.05       0  4833.2    0.12       0  4952.3    0.05       0
  4966.4    0.05       0  4973.8    0.05       0
Bank Sta=4966.4,4973.8
Exp/Cntr=0.3,0.1

Type RM Length L Ch R = 1,1232,901,901,901
BEGIN DESCRIPTION:
TANTROUGH CREEK 2.0
END DESCRIPTION:
XS GIS Cut Line= 3
      2880805.68     10223953.11      2880498.75     10224008.00
      2880305.70     10224153.10
#Sta/Elev= 30
  4688.2  894.90  4690.7  894.90  4698.4  892.37  4715.1  885.83  4720.2  885.84
  4728.8  884.33  4749.1  883.07  4810.1  880.60  4840.6  878.60  4850.7  876.87
  4871.1  878.19  4881.2  877.49  4891.7  875.41  4901.5  874.79  4911.7  874.93
  4932.0  870.87  4940.5  869.91  4945.5  868.32  4962.5  868.18  4989.1  865.25
  4989.6  862.25  4996.3  862.25  4996.8  865.25  5005.1  867.04  5013.5  867.47
  5019.7  869.00  5055.1  873.24  5069.7  874.29  5148.8  878.36  5241.5  881.53
#Mann=3,-1,0
  4688.2    0.05       0  4989.1    0.03       0  4996.8    0.05       0
Bank Sta=4989.1,4996.8
Exp/Cntr=0.3,0.1

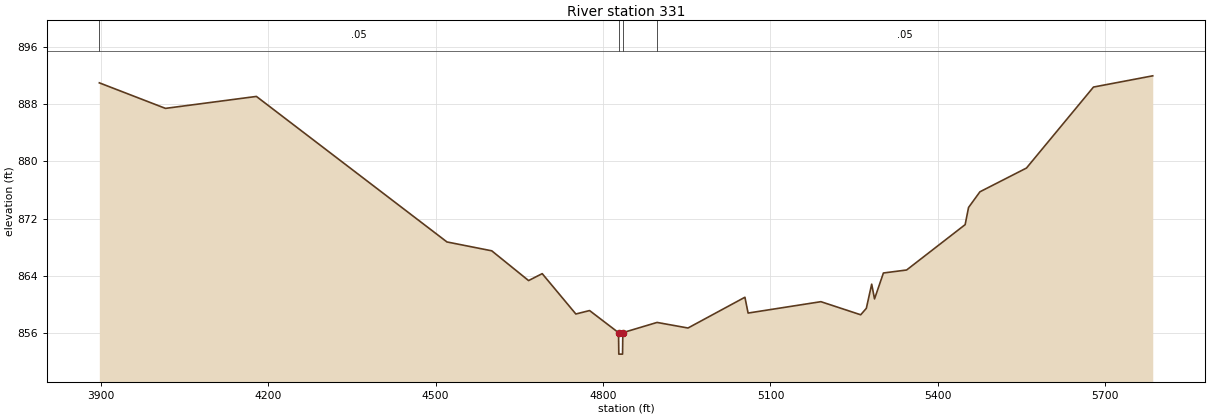
Type RM Length L Ch R = 1,331,0,0,0
BEGIN DESCRIPTION:
TANTROUGH CREEK 1.0
END DESCRIPTION:
XS GIS Cut Line= 4
      2880825.98     10223516.91      2879779.55     10223614.08
      2879657.28     10223682.89      2879528.19     10224367.49
#Sta/Elev= 30
  3897.2  890.98  4015.7  887.41  4178.7  889.08  4520.2  868.74  4600.5  867.50
  4666.5  863.34  4690.9  864.31  4751.2  858.67  4775.8  859.15  4827.7  856.06
  4828.2  853.06  4834.9  853.06  4835.4  856.06  4896.8  857.49  4952.2  856.71
  5054.2  861.01  5059.9  858.80  5190.4  860.39  5261.7  858.56  5271.8  859.46
  5281.4  862.84  5286.5  860.78  5302.4  864.40  5344.0  864.82  5448.9  871.16
  5455.0  873.56  5475.4  875.75  5558.8  879.07  5678.9  890.39  5785.1  891.96
#Mann=4,-1,0
  3897.2    0.05       0  4827.7    0.05       0  4835.4    0.05       0
  4896.8    0.05       0
Bank Sta=4827.7,4835.4
Exp/Cntr=0.3,0.1

Chan Stop Cuts=-1