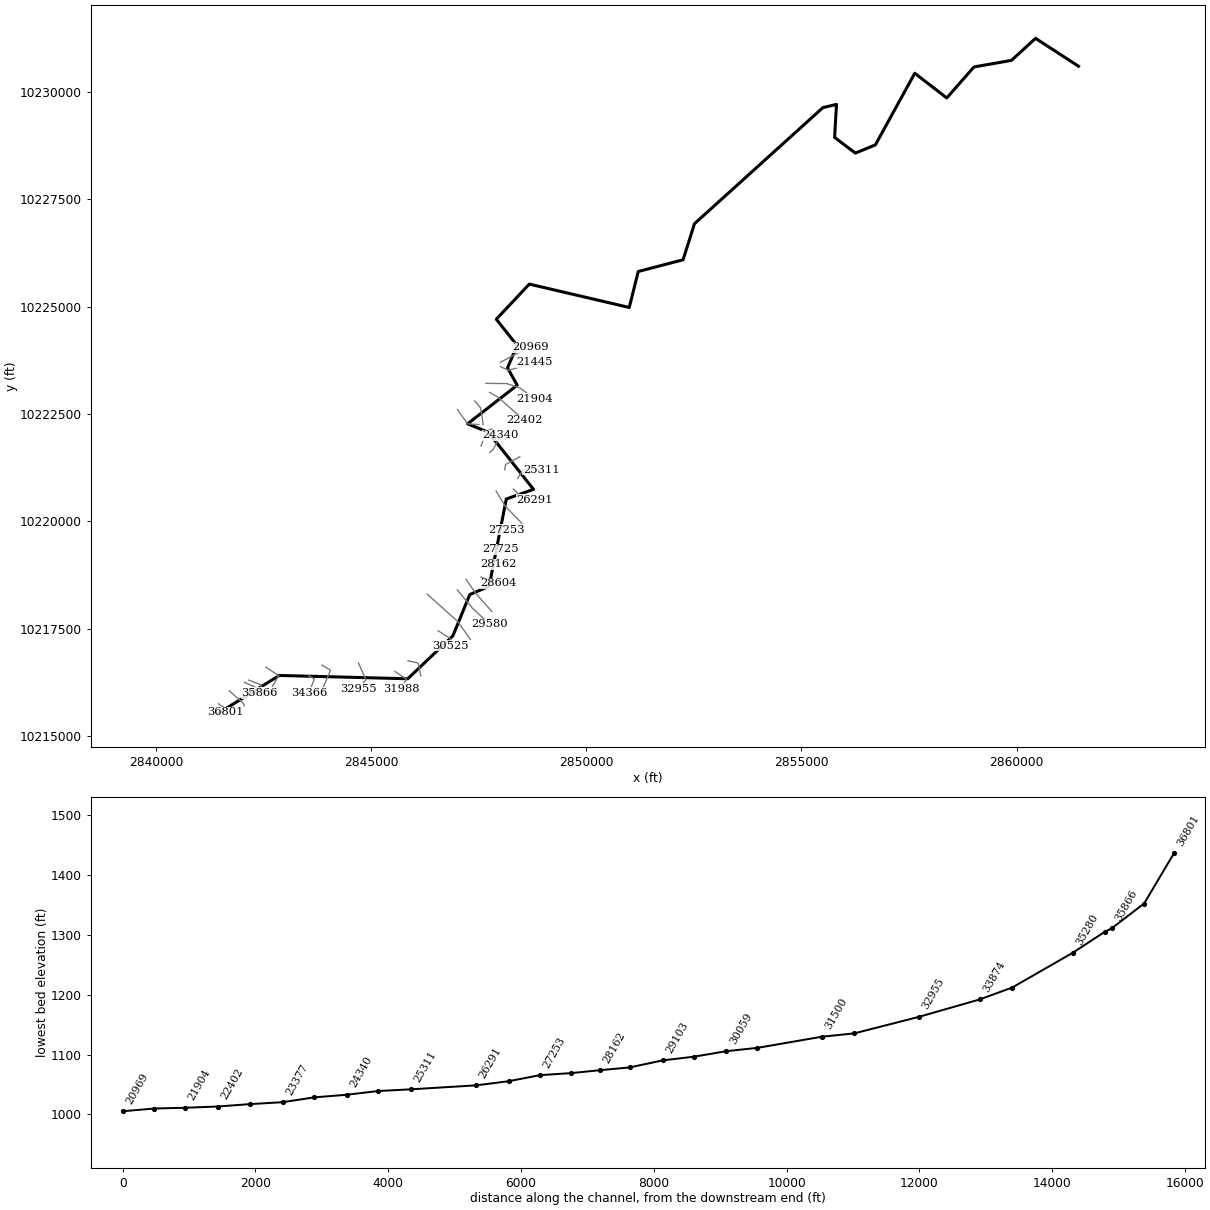
--- WATERS CREEK.prj (project) ---

Proj Title=WATERS CREEK Base Level Engineering
Current Plan=p01
Default Exp/Contr=0.3,0.1
English Units
Geom File=g01
Flow File=f01
Plan File=p01
Y Axis Title=Elevation
X Axis Title(PF)=Main Channel Distance
X Axis Title(XS)=Station
BEGIN DESCRIPTION:
WATERS CREEK
END DESCRIPTION:
DSS Export Rating Curves= 0
DSS Export Rating Curve Sorted= 0
DSS Export Volume Flow Curves= 0
DXF OffsetX= 0
DXF OffsetY= 0
DXF ScaleX= 1
DXF ScaleY= 10

--- WATERS CREEK.p01 (plan) ---

Plan Title=Multiple Run
Short Identifier=Multiple
Geom File=g01
Flow File=f01
Subcritical Flow
K Sum by GR= 0
Std Step Tol= 0.01
Critical Tol= 0.01
Num of Std Step Trials= 20
Max Error Tol= 0.3
Flow Tol Ratio= 0.001
Split Flow NTrial= 30
Split Flow Tol= 0.02
Split Flow Ratio= 0.02
Log Output Level= 0
Friction Slope Method= 1
Unsteady Friction Slope Method= 2
Unsteady Bridges Friction Slope Method= 1
Parabolic Critical Depth
Global Vel Dist=  1 , 1 , 1
Global Log Level= 0
CheckData=True
Encroach Param= -1, 0, 0, 0
BEGIN DESCRIPTION:
Multiple Run
END DESCRIPTION:

--- WATERS CREEK.f01 (steady flow) ---

Flow Title=Multiple
Program Version=4.10
Number of Profiles= 7
Profile Names=10-year,25-year,50-year,1pct_min,100-year,1pct_plu,500-year
River Rch & RM=WATERS CREEK,Reach-1         ,36801
      79     143     220     113     341    1031     895
River Rch & RM=WATERS CREEK,Reach-1         ,31988
     114     227     362     192     578    1747    1584
River Rch & RM=WATERS CREEK,Reach-1         ,27725
     130     266     431     230     694    2097    1929
River Rch & RM=WATERS CREEK,Reach-1         ,22888
     221     483     803     438    1323    3997    3827
River Rch & RM=WATERS CREEK,Reach-1         ,19061
     249     550     920     505    1524    4602    4440
River Rch & RM=WATERS CREEK,Reach-1         ,17408
     258     573     960     527    1593    4810    4652
River Rch & RM=WATERS CREEK,Reach-1         ,14186
     283     631    1061     584    1764    5327    5180
River Rch & RM=WATERS CREEK,Reach-1         ,13762
     303     682    1149     634    1915    5782    5646
River Rch & RM=WATERS CREEK,Reach-1         ,10412
     328     743    1255     695    2098    6334    6215
River Rch & RM=WATERS CREEK,Reach-1         ,5043
     336     761    1287     713    2152    6498    6383
River Rch & RM=WATERS CREEK,Reach-1         ,3144
     358     814    1380     766    2312    6983    6883
Boundary for River Rch & Prof#=WATERS CREEK,Reach-1         , 1
Up Type= 0
Dn Type= 3
Dn Slope=0.0005
Boundary for River Rch & Prof#=WATERS CREEK,Reach-1         , 2
Up Type= 0
Dn Type= 3
Dn Slope=0.0005
Boundary for River Rch & Prof#=WATERS CREEK,Reach-1         , 3
Up Type= 0
Dn Type= 3
Dn Slope=0.0005
Boundary for River Rch & Prof#=WATERS CREEK,Reach-1         , 4
Up Type= 0
Dn Type= 3
Dn Slope=0.0005
Boundary for River Rch & Prof#=WATERS CREEK,Reach-1         , 5
Up Type= 0
Dn Type= 3
Dn Slope=0.0005
Boundary for River Rch & Prof#=WATERS CREEK,Reach-1         , 6
Up Type= 0
Dn Type= 3
Dn Slope=0.0005
Boundary for River Rch & Prof#=WATERS CREEK,Reach-1         , 7
Up Type= 0
Dn Type= 3
Dn Slope=0.0005
DSS Import GetInterval= 0
DSS Import GetPeak= 0
DSS Import FillOption= 0

--- WATERS CREEK.g01 (geometry) ---

Geom Title=Existing Conditions

River Reach=WATERS CREEK,Reach-1
Reach XY= 30
      2841444.75     10215529.00      2842869.25     10216412.00
      2845851.75     10216335.00      2846901.25     10217334.00
      2847293.75     10218296.00      2847743.00     10218486.00
      2848142.50     10220520.00      2848774.00     10220745.00
      2847726.75     10222073.00      2847242.50     10222270.00
      2848395.50     10223170.00      2848170.50     10223573.00
      2848392.50     10224095.00      2847909.75     10224705.00
      2848676.75     10225523.00      2850998.75     10224979.00
      2851208.00     10225817.00      2852249.25     10226089.00
      2852514.25     10226929.00      2855498.75     10229632.00
      2855814.25     10229707.00      2855770.50     10228939.00
      2856251.75     10228573.00      2856717.50     10228764.00
      2857633.00     10230432.00      2858376.75     10229857.00
      2859008.00     10230579.00      2859880.00     10230732.00
      2860439.25     10231245.00      2861437.75     10230595.00

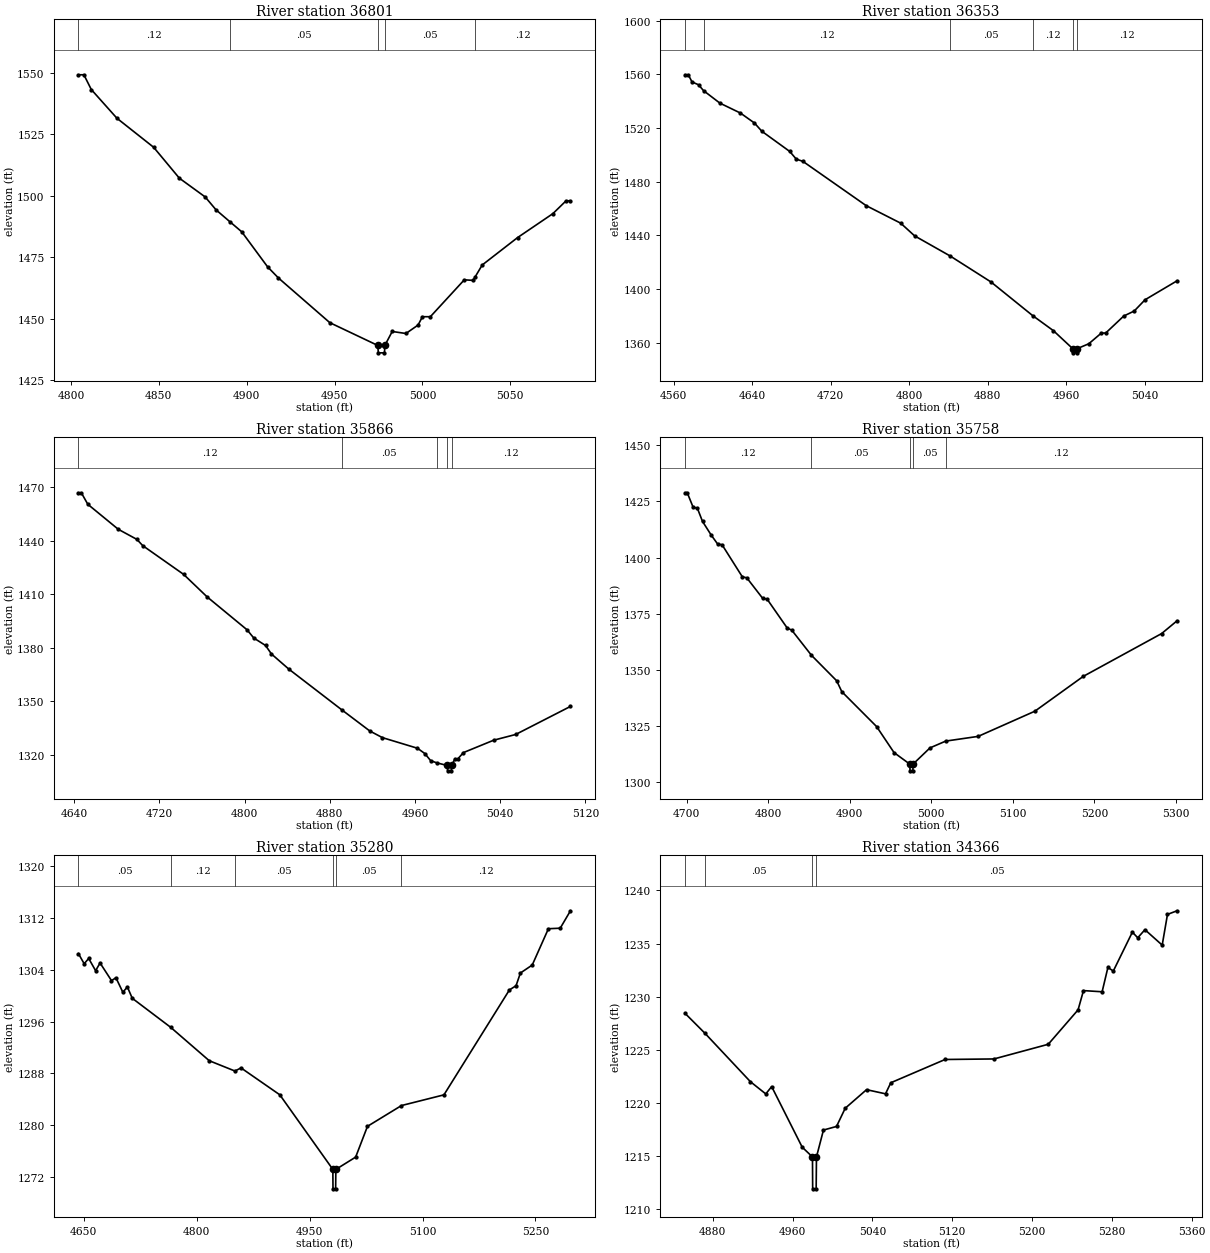
Type RM Length L Ch R = 1,36801,448,448,448
BEGIN DESCRIPTION:
WATERS CREEK 72.0
END DESCRIPTION:
XS GIS Cut Line= 3
      2841455.71     10215753.10      2841613.25     10215637.00
      2841605.69     10215553.14
#Sta/Elev= 30
  4804.3 1549.11  4807.4 1549.11  4811.6 1543.12  4826.2 1531.44  4847.1 1519.63
  4861.7 1507.09  4876.4 1499.46  4882.6 1494.20  4890.6 1489.30  4897.2 1485.29
  4911.9 1471.06  4918.1 1466.51  4947.3 1448.37  4974.6 1439.11  4974.9 1436.11
  4978.4 1436.11  4978.6 1439.11  4982.8 1444.79  4990.6 1443.97  4997.5 1447.40
  5000.0 1450.79  5004.5 1450.79  5023.8 1465.78  5028.8 1465.56  5029.8 1466.76
  5034.0 1471.81  5054.1 1482.94  5074.2 1492.68  5081.7 1497.89  5084.2 1497.89
#Mann=5,-1,0
  4804.3    0.12       0  4890.6    0.05       0  4974.6    0.05       0
  4978.6    0.05       0  5029.8    0.12       0
Bank Sta=4974.6,4978.6
Exp/Cntr=0.3,0.1

Type RM Length L Ch R = 1,36353,487,487,487
BEGIN DESCRIPTION:
WATERS CREEK 71.0
END DESCRIPTION:
XS GIS Cut Line= 3
      2841705.71     10216053.09      2842027.25     10215770.00
      2842055.69     10215703.09
#Sta/Elev= 30
  4571.6 1559.71  4574.9 1559.71  4578.7 1554.35  4585.3 1552.28  4590.4 1547.90
  4607.1 1538.56  4628.0 1531.17  4642.3 1523.73  4649.8 1517.60  4678.2 1502.55
  4684.9 1496.81  4691.6 1495.16  4756.1 1462.12  4791.2 1449.07  4805.4 1439.60
  4841.5 1424.64  4883.2 1405.22  4925.5 1380.22  4946.8 1368.88  4966.6 1355.38
  4966.8 1352.38  4970.3 1352.38  4970.6 1355.38  4982.8 1359.15  4995.6 1367.13
  5000.0 1367.13  5018.4 1379.82  5029.1 1383.57  5040.1 1391.95  5072.7 1406.09
#Mann=6,-1,0
  4571.6    0.05       0  4590.4    0.12       0  4841.5    0.05       0
  4925.5    0.12       0  4966.6    0.07       0  4970.6    0.12       0
Bank Sta=4966.6,4970.6
Exp/Cntr=0.3,0.1

Type RM Length L Ch R = 1,35866,108,108,108
BEGIN DESCRIPTION:
WATERS CREEK 70.0
END DESCRIPTION:
XS GIS Cut Line= 3
      2842055.70     10216253.10      2842380.00     10216106.00
      2842405.67     10216003.16
#Sta/Elev= 30
  4643.9 1466.89  4646.6 1466.89  4652.7 1460.43  4681.3 1446.42  4698.8 1440.75
  4704.3 1437.24  4742.7 1421.13  4764.7 1408.54  4802.2 1390.09  4808.6 1385.44
  4819.6 1381.29  4825.2 1376.48  4841.5 1368.01  4891.4 1345.11  4917.6 1333.30
  4929.4 1329.60  4962.3 1323.65  4969.2 1320.68  4974.7 1316.69  4980.3 1315.49
  4990.3 1313.98  4990.6 1310.98  4994.1 1310.98  4994.3 1313.98  4997.4 1317.55
  5000.0 1317.55  5005.5 1321.22  5033.9 1328.16  5054.5 1331.36  5106.0 1347.10
#Mann=5,-1,0
  4643.9    0.12       0  4891.4    0.05       0  4980.3    0.12       0
  4990.3    0.07       0  4994.3    0.12       0
Bank Sta=4990.3,4994.3
Exp/Cntr=0.3,0.1

Type RM Length L Ch R = 1,35758,478,478,478
BEGIN DESCRIPTION:
WATERS CREEK 69.0
END DESCRIPTION:
XS GIS Cut Line= 3
      2842155.65     10216303.12      2842438.50     10216197.00
      2842505.69     10215903.08
#Sta/Elev= 30
  4697.9 1428.88  4700.6 1428.88  4707.7 1422.52  4713.1 1421.90  4719.3 1416.12
  4730.0 1410.01  4738.0 1405.97  4743.3 1405.72  4768.2 1391.39  4773.6 1390.99
  4793.1 1381.83  4798.5 1381.50  4823.4 1368.50  4828.7 1367.70  4853.0 1356.42
  4883.9 1345.08  4890.2 1340.22  4932.9 1324.66  4954.3 1313.06  4973.6 1307.93
  4973.9 1304.93  4977.4 1304.93  4977.6 1307.93  4998.4 1315.16  5017.7 1318.19
  5057.5 1320.29  5127.1 1331.52  5186.4 1347.03  5282.6 1366.13  5301.5 1371.82
#Mann=5,-1,0
  4697.9    0.12       0  4853.0    0.05       0  4973.6    0.05       0
  4977.6    0.05       0  5017.7    0.12       0
Bank Sta=4973.6,4977.6
Exp/Cntr=0.3,0.1

Type RM Length L Ch R = 1,35280,914,914,914
BEGIN DESCRIPTION:
WATERS CREEK 68.0
END DESCRIPTION:
XS GIS Cut Line= 3
      2842555.66     10216603.13      2842855.50     10216409.00
      2842705.69     10216153.13
#Sta/Elev= 30
  4642.8 1306.50  4650.4 1304.94  4656.4 1305.76  4665.6 1303.87  4671.5 1305.06
  4686.7 1302.34  4692.6 1302.78  4701.8 1300.54  4707.8 1301.36  4714.3 1299.61
  4765.3 1295.13  4816.6 1289.97  4850.7 1288.38  4858.8 1288.86  4910.3 1284.71
  4980.8 1273.19  4981.0 1270.19  4984.5 1270.19  4984.8 1273.19  5011.1 1275.09
  5026.8 1279.84  5072.0 1283.05  5128.4 1284.70  5215.4 1300.90  5224.2 1301.55
  5230.0 1303.51  5245.7 1304.74  5267.2 1310.35  5282.9 1310.43  5296.5 1313.12
#Mann=6,-1,0
  4642.8    0.05       0  4765.3    0.12       0  4850.7    0.05       0
  4980.8    0.03       0  4984.8    0.05       0  5072.0    0.12       0
Bank Sta=4980.8,4984.8
Exp/Cntr=0.3,0.1

Type RM Length L Ch R = 1,34366,492,492,492
BEGIN DESCRIPTION:
WATERS CREEK 66.0
END DESCRIPTION:
XS GIS Cut Line= 3
      2843555.66     10216403.13      2843681.00     10216325.00
      2843555.69     10216003.13
#Sta/Elev= 30
  4852.3 1228.44  4872.2 1226.57  4917.8 1222.01  4933.2 1220.86  4939.1 1221.55
  4969.7 1215.85  4980.0 1214.93  4980.2 1211.93  4983.7 1211.93  4984.0 1214.93
  4991.0 1217.46  5004.1 1217.80  5012.8 1219.51  5034.2 1221.26  5053.2 1220.87
  5058.5 1221.91  5112.9 1224.10  5161.9 1224.15  5216.3 1225.53  5246.2 1228.77
  5251.6 1230.58  5270.3 1230.47  5276.1 1232.76  5281.5 1232.42  5300.6 1236.08
  5306.0 1235.55  5313.2 1236.31  5330.5 1234.86  5335.8 1237.75  5345.4 1238.09
#Mann=4,-1,0
  4852.3    0.12       0  4872.2    0.05       0  4980.0    0.03       0
  4984.0    0.05       0
Bank Sta=4980,4984
Exp/Cntr=0.3,0.1

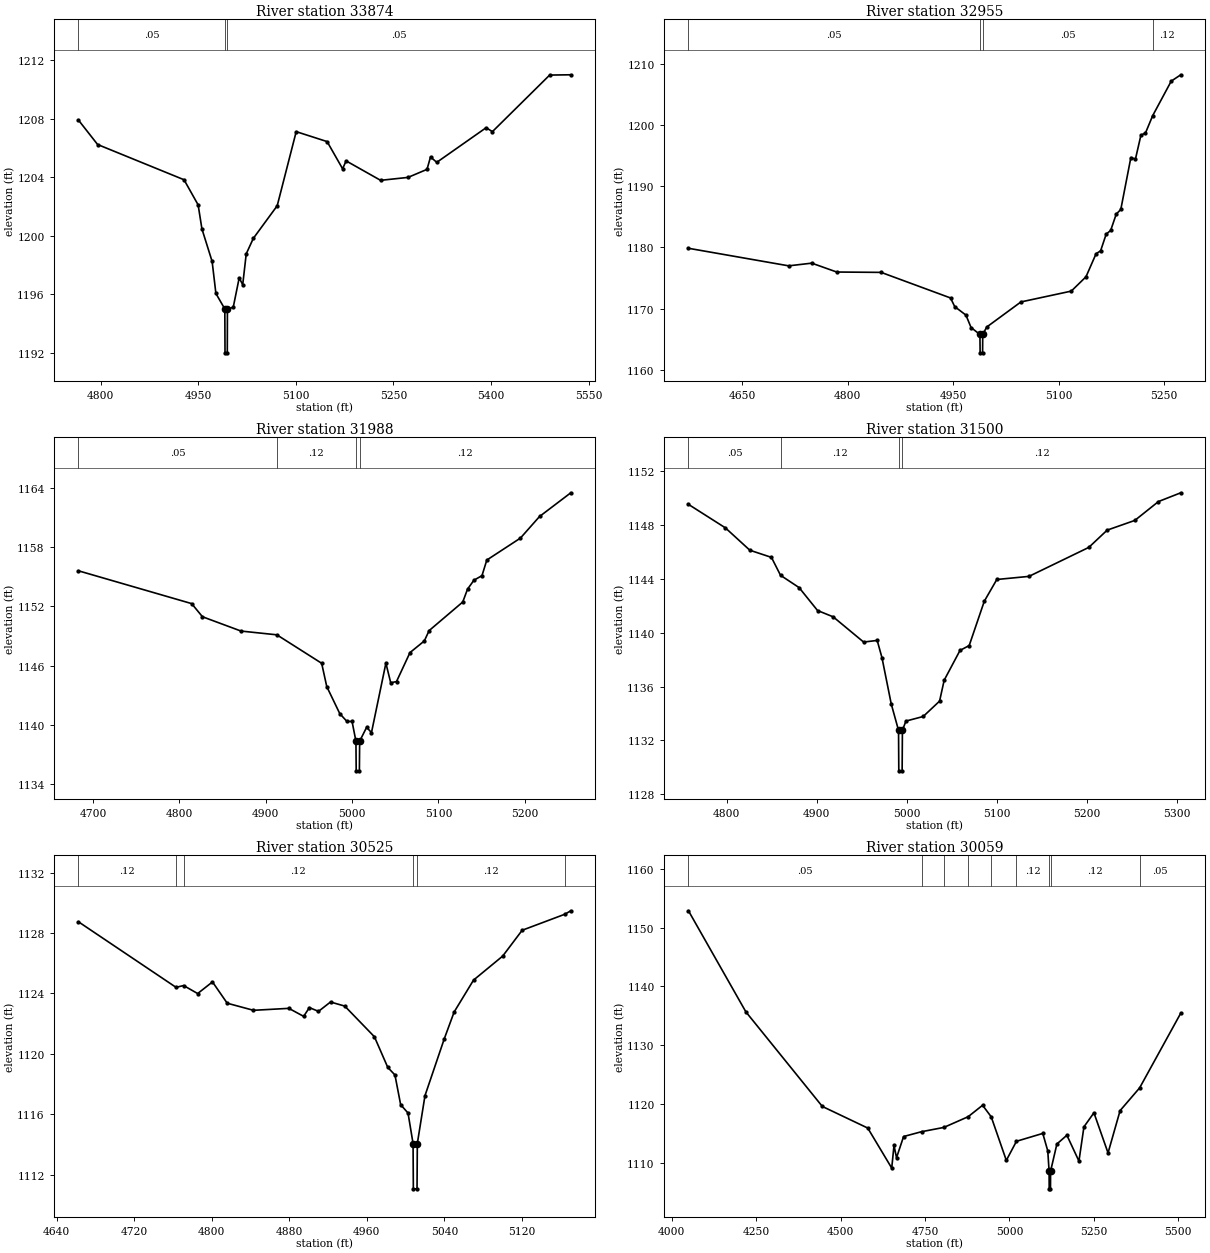
Type RM Length L Ch R = 1,33874,919,919,919
BEGIN DESCRIPTION:
WATERS CREEK 65.0
END DESCRIPTION:
XS GIS Cut Line= 3
      2843855.64     10216653.14      2844057.75     10216535.00
      2843855.70     10216053.15
#Sta/Elev= 30
  4765.9 1207.90  4795.3 1206.23  4928.1 1203.82  4949.8 1202.10  4955.6 1200.46
  4971.3 1198.23  4977.1 1196.04  4990.8 1194.98  4991.1 1191.98  4994.6 1191.98
  4994.8 1194.98  5003.7 1195.09  5012.9 1197.11  5018.3 1196.64  5023.7 1198.75
  5034.6 1199.81  5071.3 1202.04  5100.5 1207.11  5148.0 1206.43  5171.8 1204.57
  5177.2 1205.11  5230.2 1203.78  5272.3 1203.98  5301.5 1204.53  5306.9 1205.38
  5316.5 1205.01  5392.4 1207.38  5402.0 1207.11  5490.0 1210.98  5522.5 1211.00
#Mann=3,-1,0
  4765.9    0.05       0  4990.8    0.05       0  4994.8    0.05       0
Bank Sta=4990.8,4994.8
Exp/Cntr=0.3,0.1

Type RM Length L Ch R = 1,32955,967,967,967
BEGIN DESCRIPTION:
WATERS CREEK 63.0
END DESCRIPTION:
XS GIS Cut Line= 3
      2844705.67     10216703.14      2844880.00     10216314.00
      2844705.69     10216103.12
#Sta/Elev= 30
  4573.6 1179.85  4716.1 1176.98  4748.9 1177.42  4784.4 1175.97  4847.6 1175.91
  4946.2 1171.73  4952.2 1170.31  4968.1 1168.93  4975.4 1166.90  4988.0 1165.76
  4988.3 1162.76  4991.8 1162.76  4992.0 1165.76  4997.7 1166.98  5046.3 1171.08
  5117.9 1172.85  5138.8 1175.19  5153.1 1178.95  5159.6 1179.44  5167.5 1182.16
  5173.9 1182.77  5181.8 1185.43  5188.3 1186.20  5202.6 1194.68  5209.1 1194.42
  5216.9 1198.33  5223.4 1198.70  5233.6 1201.52  5260.0 1207.17  5273.6 1208.21
#Mann=4,-1,0
  4573.6    0.05       0  4988.0    0.03       0  4992.0    0.05       0
  5233.6    0.12       0
Bank Sta=4988,4992
Exp/Cntr=0.3,0.1

Type RM Length L Ch R = 1,31988,488,488,488
BEGIN DESCRIPTION:
WATERS CREEK 61.0
END DESCRIPTION:
XS GIS Cut Line= 3
      2845555.71     10216503.10      2845820.50     10216329.00
      2845705.68     10216103.11
#Sta/Elev= 30
  4683.1 1155.60  4814.2 1152.28  4826.7 1150.95  4871.4 1149.50  4912.9 1149.12
  4964.8 1146.24  4970.7 1143.88  4985.8 1141.14  4994.1 1140.35  5000.0 1140.35
  5004.5 1138.35  5004.8 1135.35  5008.5 1135.35  5008.8 1138.35  5016.9 1139.76
  5022.5 1139.22  5039.2 1146.25  5044.8 1144.26  5051.5 1144.39  5067.1 1147.32
  5083.7 1148.50  5089.3 1149.55  5128.2 1152.44  5133.8 1153.75  5141.2 1154.65
  5150.5 1155.11  5156.1 1156.69  5195.0 1158.91  5217.2 1161.10  5253.4 1163.50
#Mann=4,-1,0
  4683.1    0.05       0  4912.9    0.12       0  5004.5    0.07       0
  5008.8    0.12       0
Bank Sta=5004.5,5008.8
Exp/Cntr=0.3,0.1

Type RM Length L Ch R = 1,31500,975,975,975
BEGIN DESCRIPTION:
WATERS CREEK 60.0
END DESCRIPTION:
XS GIS Cut Line= 3
      2845855.67     10216753.12      2846092.50     10216701.00
      2846155.68     10216403.13
#Sta/Elev= 30
  4757.5 1149.51  4798.5 1147.77  4825.7 1146.11  4849.7 1145.58  4859.8 1144.25
  4880.4 1143.34  4900.9 1141.64  4918.3 1141.17  4952.1 1139.30  4967.2 1139.42
  4972.5 1138.14  4982.8 1134.71  4990.9 1132.75  4991.2 1129.75  4994.9 1129.75
  4995.2 1132.75  4999.1 1133.44  5018.3 1133.78  5036.5 1134.92  5041.6 1136.47
  5059.2 1138.68  5069.4 1139.04  5086.2 1142.33  5100.1 1143.94  5135.8 1144.17
  5202.3 1146.32  5222.7 1147.60  5253.4 1148.32  5279.7 1149.72  5304.5 1150.37
#Mann=4,-1,0
  4757.5    0.05       0  4859.8    0.12       0  4990.9    0.07       0
  4995.2    0.12       0
Bank Sta=4990.9,4995.2
Exp/Cntr=0.3,0.1

Type RM Length L Ch R = 1,30525,466,466,466
BEGIN DESCRIPTION:
WATERS CREEK 58.0
END DESCRIPTION:
XS GIS Cut Line= 3
      2846555.70     10217453.10      2846841.25     10217273.00
      2846855.68     10217103.11
#Sta/Elev= 30
  4662.4 1128.74  4763.1 1124.40  4770.9 1124.52  4785.4 1123.99  4800.7 1124.76
  4815.9 1123.35  4843.0 1122.88  4879.5 1123.01  4894.8 1122.48  4900.7 1123.06
  4910.1 1122.81  4922.5 1123.43  4937.2 1123.16  4967.8 1121.13  4981.6 1119.10
  4989.0 1118.60  4994.9 1116.63  5002.5 1116.08  5007.7 1114.06  5008.0 1111.06
  5011.8 1111.06  5012.1 1114.06  5020.0 1117.23  5040.0 1121.01  5050.1 1122.77
  5070.1 1124.88  5100.2 1126.47  5120.3 1128.18  5164.3 1129.24  5170.5 1129.47
#Mann=6,-1,0
  4662.4    0.12       0  4763.1    0.05       0  4770.9    0.12       0
  5007.7    0.07       0  5012.1    0.12       0  5164.3    0.05       0
Bank Sta=5007.7,5012.1
Exp/Cntr=0.3,0.1

Type RM Length L Ch R = 1,30059,479,479,479
BEGIN DESCRIPTION:
WATERS CREEK 57.0
END DESCRIPTION:
XS GIS Cut Line= 3
      2846305.69     10218303.10      2847013.00     10217668.00
      2847305.66     10217253.14
#Sta/Elev= 30
  4049.4 1152.85  4219.5 1135.65  4445.9 1119.56  4580.5 1115.88  4651.5 1109.07
  4658.2 1112.93  4665.7 1110.83  4686.6 1114.44  4739.7 1115.26  4805.9 1115.99
  4877.8 1117.81  4920.6 1119.76  4946.2 1117.79  4990.9 1110.38  5020.9 1113.63
  5098.9 1114.97  5113.7 1111.99  5117.6 1108.54  5117.9 1105.54  5121.7 1105.54
  5122.0 1108.54  5140.7 1113.17  5170.3 1114.66  5206.0 1110.26  5220.8 1116.09
  5250.4 1118.48  5292.2 1111.65  5327.9 1118.85  5385.8 1122.72  5507.7 1135.44
#Mann=9,-1,0
  4049.4    0.05       0  4739.7    0.12       0  4805.9    0.05       0
  4877.8    0.12       0  4946.2    0.05       0  5020.9    0.12       0
  5117.6    0.03       0  5122.0    0.12       0  5385.8    0.05       0
Bank Sta=5117.6,5122
Exp/Cntr=0.3,0.1

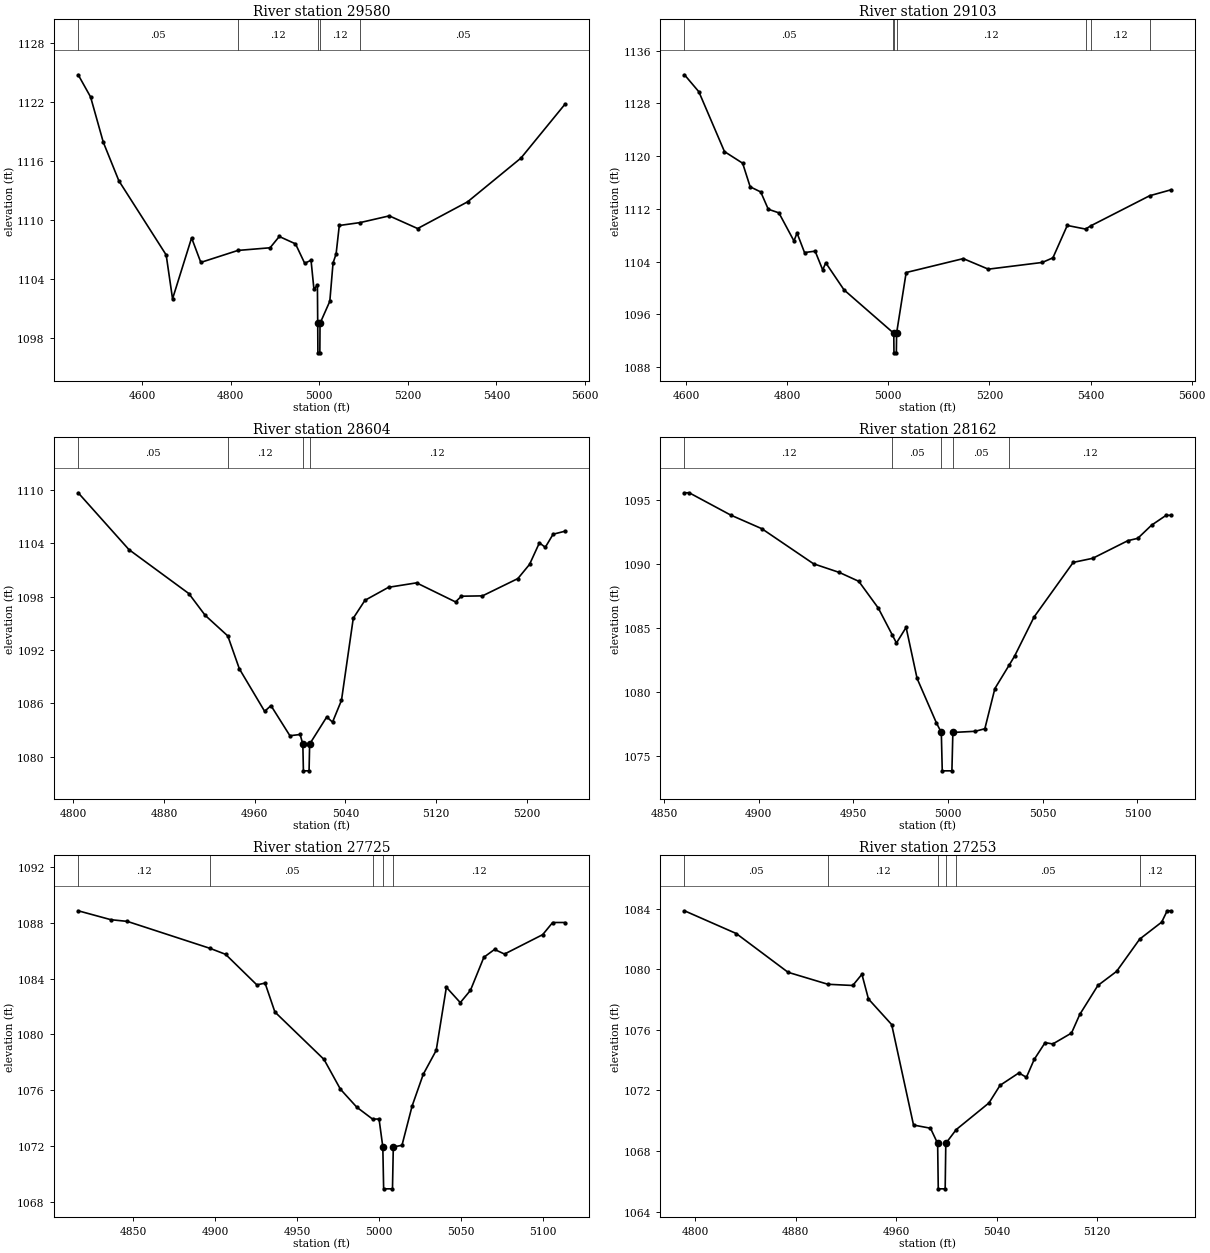
Type RM Length L Ch R = 1,29580,477,477,477
BEGIN DESCRIPTION:
WATERS CREEK 56.0
END DESCRIPTION:
XS GIS Cut Line= 3
      2847005.65     10218403.15      2847352.00     10217983.00
      2847755.67     10217603.13
#Sta/Elev= 30
  4455.5 1124.81  4483.5 1122.55  4512.2 1117.94  4547.4 1114.01  4654.2 1106.46
  4668.6 1101.99  4711.6 1108.20  4732.4 1105.70  4816.2 1106.92  4888.8 1107.19
  4909.6 1108.34  4946.2 1107.59  4967.0 1105.61  4981.3 1105.92  4987.8 1102.99
  4995.7 1103.38  4996.4 1099.49  4996.8 1096.49  5001.2 1096.49  5001.6 1099.49
  5023.7 1101.74  5031.0 1105.64  5037.9 1106.56  5045.1 1109.46  5092.6 1109.76
  5158.0 1110.44  5222.0 1109.15  5334.8 1111.87  5455.4 1116.33  5554.3 1121.79
#Mann=5,-1,0
  4455.5    0.05       0  4816.2    0.12       0  4996.4    0.07       0
  5001.6    0.12       0  5092.6    0.05       0
Bank Sta=4996.4,5001.6
Exp/Cntr=0.3,0.1

Type RM Length L Ch R = 1,29103,499,499,499
BEGIN DESCRIPTION:
WATERS CREEK 55.0
END DESCRIPTION:
XS GIS Cut Line= 3
      2847205.70     10218653.09      2847434.00     10218321.00
      2847805.71     10217903.09
#Sta/Elev= 30
  4597.0 1132.34  4625.4 1129.77  4676.1 1120.69  4712.0 1118.93  4726.9 1115.35
  4747.8 1114.57  4762.7 1111.95  4783.7 1111.40  4813.5 1107.14  4819.6 1108.34
  4834.4 1105.38  4855.4 1105.59  4870.3 1102.75  4876.4 1103.82  4912.5 1099.72
  5009.7 1093.22  5010.9 1093.17  5011.3 1090.17  5016.0 1090.17  5016.5 1093.17
  5035.4 1102.35  5148.3 1104.46  5197.9 1102.86  5304.6 1103.88  5325.6 1104.58
  5354.0 1109.49  5390.1 1108.94  5400.7 1109.44  5516.8 1113.99  5559.3 1114.90
#Mann=7,-1,0
  4597.0    0.05       0  5009.7    0.12       0  5010.9    0.05       0
  5016.5    0.12       0  5390.1    0.05       0  5400.7    0.12       0
  5516.8    0.05       0
Bank Sta=5010.9,5016.5
Exp/Cntr=0.3,0.1

Type RM Length L Ch R = 1,28604,442,442,442
BEGIN DESCRIPTION:
WATERS CREEK 54.0
END DESCRIPTION:
XS GIS Cut Line= 3
      2847555.65     10218703.13      2847730.50     10218615.00
      2847955.65     10218553.12
#Sta/Elev= 30
  4804.2 1109.65  4849.0 1103.27  4901.8 1098.34  4916.2 1095.90  4936.2 1093.58
  4946.4 1089.89  4968.7 1085.12  4974.3 1085.76  4991.0 1082.38  5000.0 1082.52
  5002.4 1081.44  5002.9 1078.44  5007.9 1078.44  5008.4 1081.44  5023.5 1084.49
  5028.6 1083.91  5036.5 1086.36  5046.9 1095.57  5057.2 1097.58  5078.0 1099.04
  5102.7 1099.54  5137.1 1097.40  5142.3 1098.04  5160.9 1098.08  5192.1 1100.02
  5202.4 1101.61  5211.1 1104.03  5216.3 1103.53  5223.2 1105.00  5233.5 1105.33
#Mann=4,-1,0
  4804.2    0.05       0  4936.2    0.12       0  5002.4    0.07       0
  5008.4    0.12       0
Bank Sta=5002.4,5008.4
Exp/Cntr=0.3,0.1

Type RM Length L Ch R = 1,28162,437,437,437
BEGIN DESCRIPTION:
WATERS CREEK 53.0
END DESCRIPTION:
XS GIS Cut Line= 3
      2847705.69     10219003.11      2847841.75     10219033.00
      2847955.69     10219003.11
#Sta/Elev= 30
  4860.7 1095.58  4863.2 1095.58  4885.1 1093.84  4901.6 1092.77  4928.9 1090.03
  4942.6 1089.35  4952.8 1088.66  4963.1 1086.57  4970.6 1084.44  4972.7 1083.84
  4977.8 1085.06  4983.6 1081.07  4993.8 1077.60  4996.4 1076.85  4996.9 1073.85
  5002.0 1073.85  5002.5 1076.85  5014.3 1076.94  5019.4 1077.14  5024.7 1080.28
  5032.4 1082.15  5035.1 1082.81  5045.4 1085.87  5066.1 1090.14  5076.4 1090.46
  5095.0 1091.84  5100.2 1092.02  5107.5 1093.05  5115.2 1093.82  5117.8 1093.82
#Mann=5,-1,0
  4860.7    0.12       0  4970.6    0.05       0  4996.4    0.05       0
  5002.5    0.05       0  5032.4    0.12       0
Bank Sta=4996.4,5002.5
Exp/Cntr=0.3,0.1

Type RM Length L Ch R = 1,27725,472,472,472
BEGIN DESCRIPTION:
WATERS CREEK 52.0
END DESCRIPTION:
XS GIS Cut Line= 3
      2847755.73     10219453.11      2847939.25     10219445.00
      2848005.69     10219353.10
#Sta/Elev= 30
  4816.3 1088.86  4836.3 1088.22  4846.3 1088.10  4897.0 1086.16  4906.3 1085.74
  4925.4 1083.55  4930.4 1083.68  4936.4 1081.61  4966.4 1078.21  4976.4 1076.08
  4986.4 1074.79  4996.0 1073.94  5000.0 1073.94  5002.3 1071.94  5002.8 1068.94
  5008.2 1068.94  5008.7 1071.94  5014.0 1072.06  5020.2 1074.88  5027.0 1077.15
  5034.9 1078.86  5041.1 1083.38  5049.6 1082.28  5055.8 1083.16  5064.0 1085.53
  5070.5 1086.09  5076.6 1085.76  5099.9 1087.15  5106.0 1088.02  5113.4 1088.02
#Mann=5,-1,0
  4816.3    0.12       0  4897.0    0.05       0  4996.0    0.12       0
  5002.3    0.07       0  5008.7    0.12       0
Bank Sta=5002.3,5008.7
Exp/Cntr=0.3,0.1

Type RM Length L Ch R = 1,27253,471,471,471
BEGIN DESCRIPTION:
WATERS CREEK 51.0
END DESCRIPTION:
XS GIS Cut Line= 3
      2847805.70     10219853.12      2848008.00     10219904.00
      2848155.72     10219803.09
#Sta/Elev= 30
  4791.4 1083.85  4832.6 1082.35  4873.9 1079.79  4905.6 1079.00  4925.4 1078.92
  4932.7 1079.66  4937.9 1078.03  4956.4 1076.34  4973.8 1069.71  4987.3 1069.50
  4993.0 1068.50  4993.5 1065.50  4999.0 1065.50  4999.5 1068.50  5007.8 1069.41
  5033.9 1071.17  5042.7 1072.33  5057.7 1073.15  5063.7 1072.86  5069.9 1074.04
  5078.6 1075.15  5084.7 1075.06  5099.6 1075.78  5106.2 1077.01  5120.6 1078.92
  5135.5 1079.85  5153.9 1081.98  5171.4 1083.10  5175.8 1083.85  5178.9 1083.85
#Mann=6,-1,0
  4791.4    0.05       0  4905.6    0.12       0  4993.0    0.07       0
  4999.5    0.12       0  5007.8    0.05       0  5153.9    0.12       0
Bank Sta=4993,4999.5
Exp/Cntr=0.3,0.1

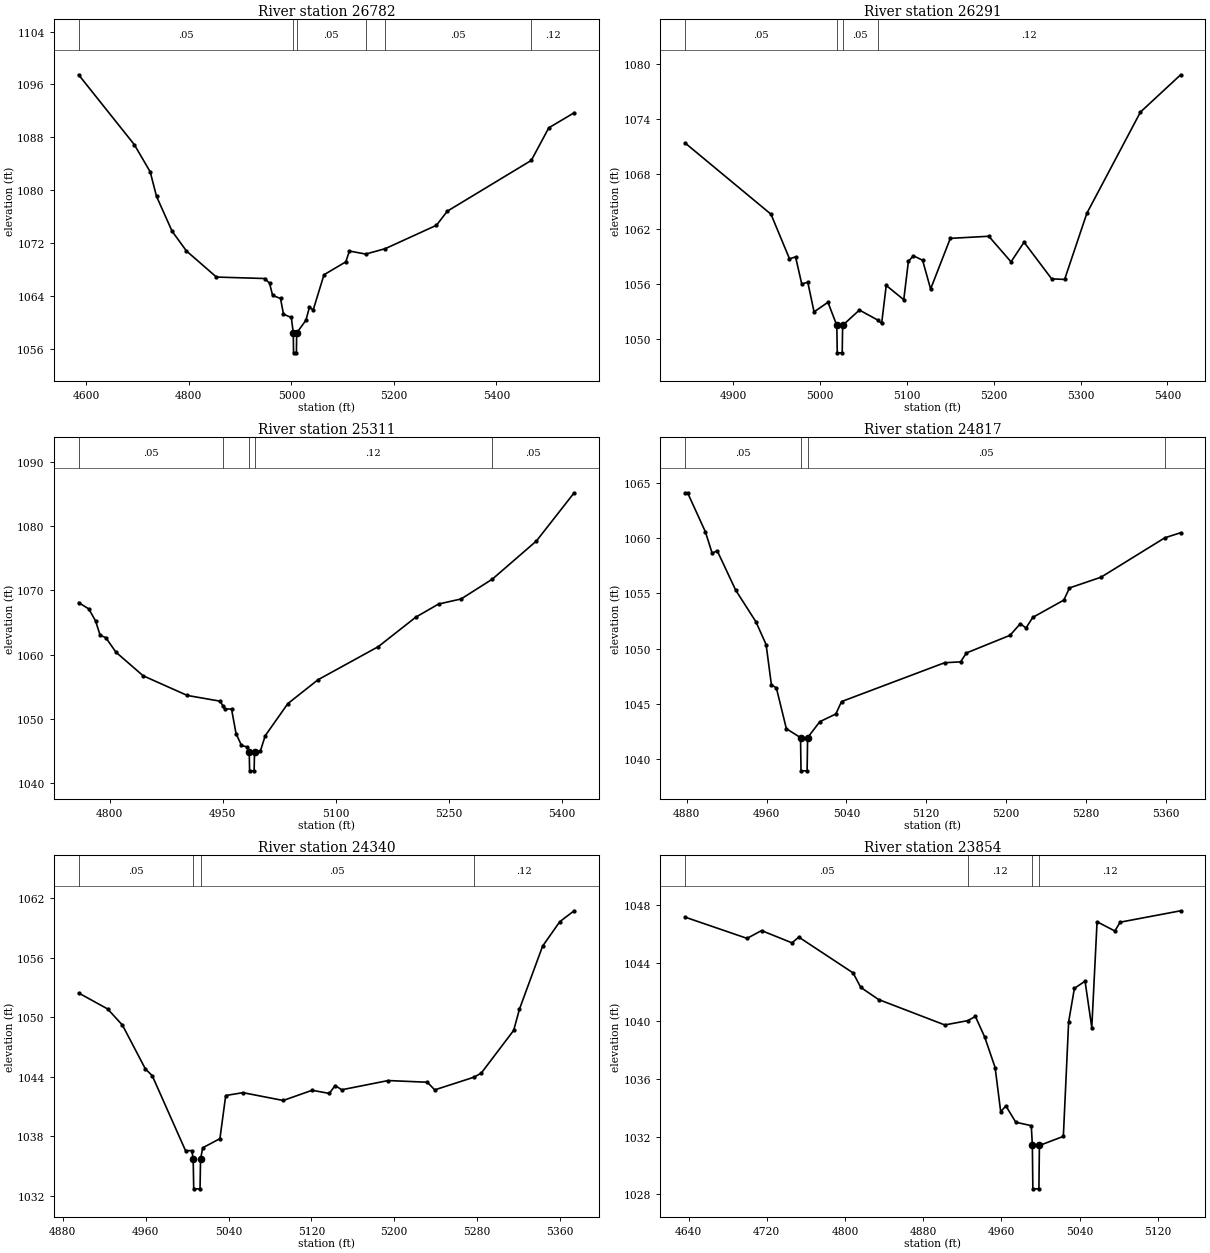
Type RM Length L Ch R = 1,26782,491,491,491
BEGIN DESCRIPTION:
WATERS CREEK 50.0
END DESCRIPTION:
XS GIS Cut Line= 3
      2847905.70     10220703.09      2848120.50     10220348.00
      2848505.66     10219953.14
#Sta/Elev= 30
  4585.0 1097.47  4693.6 1086.90  4724.6 1082.78  4736.9 1079.07  4767.3 1073.79
  4795.3 1070.80  4853.8 1066.85  4947.8 1066.63  4957.4 1065.93  4963.3 1064.08
  4978.8 1063.61  4984.6 1061.23  4999.9 1060.73  5003.7 1058.38  5004.2 1055.38
  5009.8 1055.38  5010.3 1058.38  5028.3 1060.31  5035.3 1062.30  5042.5 1061.86
  5063.6 1067.20  5106.1 1069.15  5113.2 1070.79  5145.0 1070.33  5183.1 1071.15
  5283.0 1074.69  5304.1 1076.82  5468.0 1084.51  5502.1 1089.44  5551.6 1091.72
#Mann=6,-1,0
  4585.0    0.05       0  5003.7    0.05       0  5010.3    0.05       0
  5145.0    0.12       0  5183.1    0.05       0  5468.0    0.12       0
Bank Sta=5003.7,5010.3
Exp/Cntr=0.3,0.1

Type RM Length L Ch R = 1,26291,980,980,980
BEGIN DESCRIPTION:
WATERS CREEK 49.0
END DESCRIPTION:
XS GIS Cut Line= 3
      2848305.72     10220753.08      2848414.25     10220642.00
      2848805.64     10220503.13
#Sta/Elev= 30
  4844.7 1071.39  4943.6 1063.60  4964.9 1058.73  4971.9 1058.93  4979.0 1055.98
  4986.0 1056.15  4993.2 1052.92  5009.2 1053.97  5019.4 1051.44  5019.9 1048.44
  5025.6 1048.44  5026.1 1051.44  5045.4 1053.12  5066.8 1052.01  5071.0 1051.65
  5076.3 1055.81  5096.5 1054.25  5101.8 1058.44  5107.6 1059.06  5118.2 1058.56
  5127.4 1055.42  5150.1 1060.96  5194.4 1061.19  5220.0 1058.39  5235.0 1060.54
  5266.8 1056.53  5281.7 1056.47  5307.3 1063.70  5369.0 1074.77  5415.3 1078.85
#Mann=4,-1,0
  4844.7    0.05       0  5019.4    0.05       0  5026.1    0.05       0
  5066.8    0.12       0
Bank Sta=5019.4,5026.1
Exp/Cntr=0.3,0.1

Type RM Length L Ch R = 1,25311,494,494,494
BEGIN DESCRIPTION:
WATERS CREEK 48.0
END DESCRIPTION:
XS GIS Cut Line= 3
      2848405.71     10221003.14      2848539.25     10221204.00
      2848955.65     10221203.11
#Sta/Elev= 30
  4758.8 1068.11  4772.3 1067.12  4781.3 1065.24  4787.3 1063.02  4794.8 1062.64
  4808.4 1060.36  4844.4 1056.69  4902.9 1053.62  4946.7 1052.72  4950.0 1052.04
  4952.7 1051.49  4961.7 1051.50  4967.7 1047.66  4974.9 1045.82  4982.7 1045.56
  4985.2 1044.85  4985.7 1041.85  4991.7 1041.85  4992.2 1044.85  5000.0 1044.94
  5006.4 1047.33  5036.4 1052.34  5076.4 1056.06  5156.4 1061.23  5206.4 1065.85
  5236.4 1067.88  5266.4 1068.68  5307.8 1071.77  5366.4 1077.74  5416.4 1085.25
#Mann=5,-1,0
  4758.8    0.05       0  4950.0    0.12       0  4985.2    0.07       0
  4992.2    0.12       0  5307.8    0.05       0
Bank Sta=4985.2,4992.2
Exp/Cntr=0.3,0.1

Type RM Length L Ch R = 1,24817,477,477,477
BEGIN DESCRIPTION:
WATERS CREEK 47.0
END DESCRIPTION:
XS GIS Cut Line= 3
      2848105.69     10221203.14      2848126.75     10221323.00
      2848455.67     10221503.10
#Sta/Elev= 30
  4878.3 1064.10  4880.8 1064.10  4898.6 1060.58  4905.4 1058.64  4910.5 1058.86
  4929.0 1055.30  4949.3 1052.44  4959.5 1050.38  4964.8 1046.75  4969.8 1046.46
  4979.8 1042.78  4994.0 1041.97  4994.5 1038.97  5000.6 1038.97  5001.1 1041.97
  5013.3 1043.41  5029.4 1044.11  5035.1 1045.23  5138.4 1048.74  5154.5 1048.82
  5160.2 1049.62  5204.0 1051.22  5214.3 1052.27  5220.0 1051.88  5226.8 1052.84
  5257.9 1054.40  5263.6 1055.50  5295.2 1056.47  5359.1 1060.03  5375.0 1060.49
#Mann=4,-1,0
  4878.3    0.05       0  4994.0    0.05       0  5001.1    0.05       0
  5359.1    0.12       0
Bank Sta=4994,5001.1
Exp/Cntr=0.3,0.1

Type RM Length L Ch R = 1,24340,486,486,486
BEGIN DESCRIPTION:
WATERS CREEK 46.0
END DESCRIPTION:
XS GIS Cut Line= 3
      2847755.69     10221603.12      2847836.25     10221670.00
      2848005.67     10222003.09
#Sta/Elev= 30
  4895.3 1052.47  4923.3 1050.86  4937.6 1049.23  4959.8 1044.80  4966.3 1044.14
  4998.5 1036.57  5004.6 1036.57  5005.9 1035.72  5006.4 1032.72  5012.5 1032.72
  5013.0 1035.72  5015.1 1036.86  5031.7 1037.78  5037.3 1042.13  5053.9 1042.42
  5092.8 1041.63  5120.7 1042.66  5137.3 1042.34  5142.9 1043.14  5149.3 1042.71
  5194.2 1043.64  5231.9 1043.47  5239.1 1042.70  5277.0 1043.98  5284.0 1044.39
  5315.3 1048.70  5320.9 1050.85  5343.2 1057.19  5359.8 1059.66  5373.7 1060.76
#Mann=4,-1,0
  4895.3    0.05       0  5005.9    0.05       0  5013.0    0.05       0
  5277.0    0.12       0
Bank Sta=5005.9,5013
Exp/Cntr=0.3,0.1

Type RM Length L Ch R = 1,23854,477,477,477
BEGIN DESCRIPTION:
WATERS CREEK 45.0
END DESCRIPTION:
XS GIS Cut Line= 3
      2847555.68     10221753.10      2847673.75     10222097.00
      2847805.71     10222153.12
#Sta/Elev= 30
  4636.4 1047.18  4699.8 1045.71  4714.6 1046.25  4745.8 1045.40  4752.7 1045.80
  4808.3 1043.32  4816.1 1042.32  4834.3 1041.48  4902.1 1039.72  4925.7 1040.02
  4933.4 1040.31  4943.0 1038.87  4953.6 1036.77  4959.3 1033.71  4964.6 1034.12
  4974.7 1032.99  4990.6 1032.75  4991.7 1031.38  4992.2 1028.38  4998.4 1028.38
  4998.9 1031.38  5023.4 1032.01  5028.8 1039.93  5034.7 1042.25  5045.6 1042.75
  5052.5 1039.54  5057.9 1046.86  5076.1 1046.22  5081.5 1046.83  5143.4 1047.62
#Mann=4,-1,0
  4636.4    0.05       0  4925.7    0.12       0  4991.7    0.07       0
  4998.9    0.12       0
Bank Sta=4991.7,4998.9
Exp/Cntr=0.3,0.1

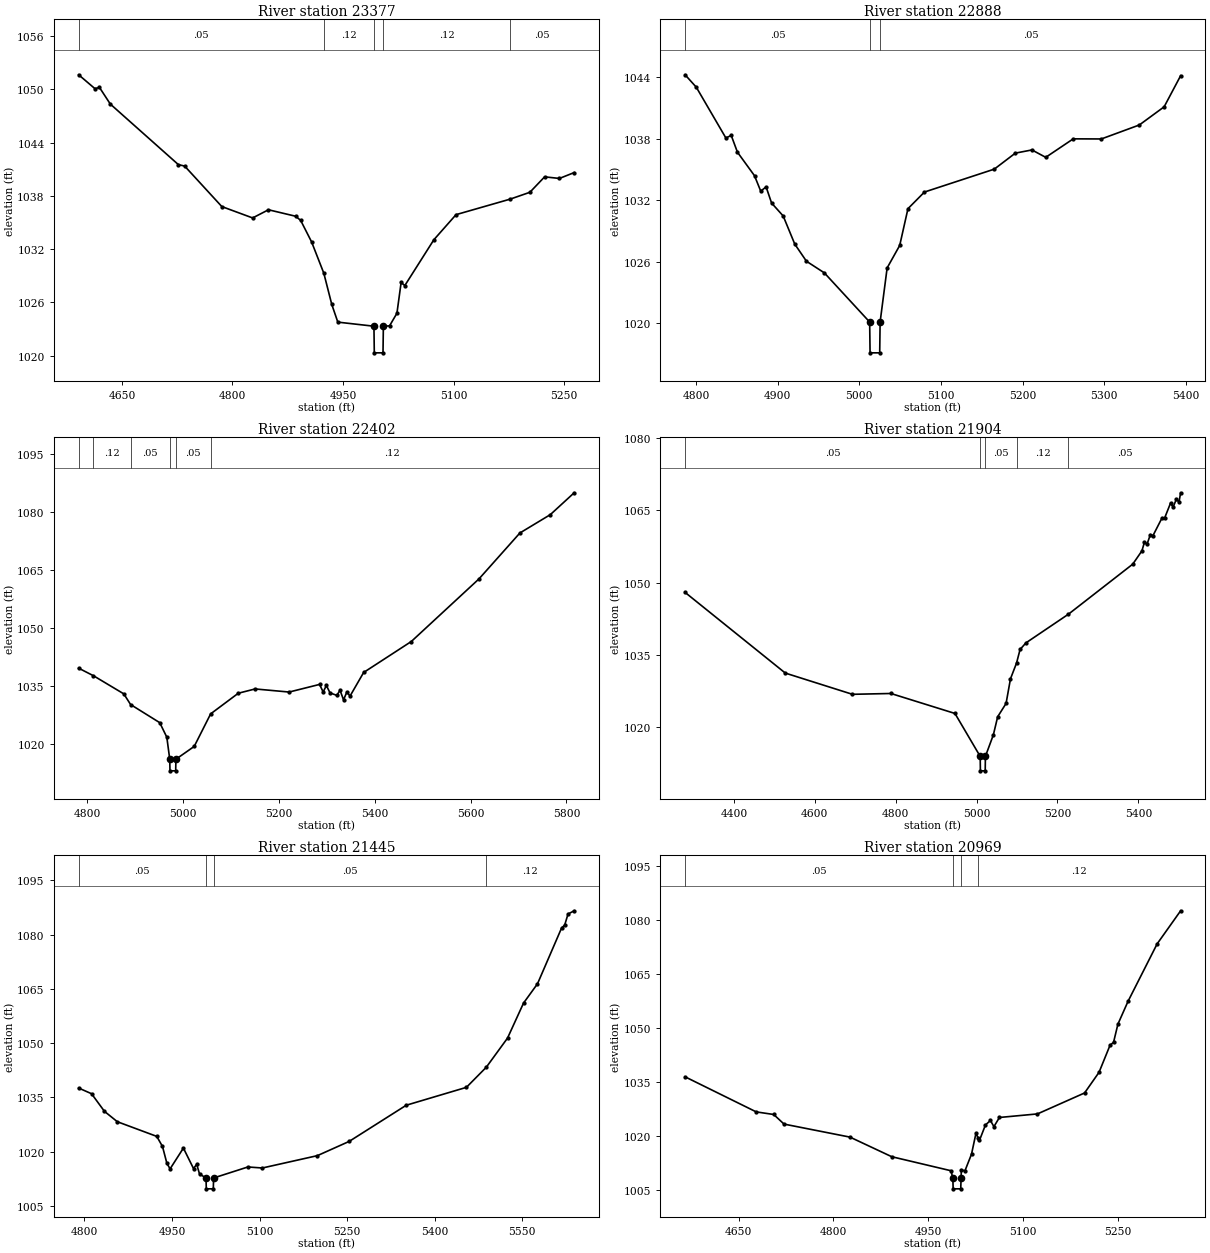
Type RM Length L Ch R = 1,23377,489,489,489
BEGIN DESCRIPTION:
WATERS CREEK 44.0
END DESCRIPTION:
XS GIS Cut Line= 3
      2847005.69     10222603.10      2847242.50     10222270.00
      2847505.66     10222253.11
#Sta/Elev= 30
  4591.3 1051.64  4613.4 1050.08  4619.6 1050.21  4634.3 1048.34  4726.6 1041.52
  4735.2 1041.35  4785.6 1036.79  4827.4 1035.51  4848.9 1036.43  4885.8 1035.70
  4892.6 1035.23  4907.4 1032.81  4924.0 1029.28  4934.8 1025.76  4943.0 1023.77
  4992.0 1023.31  4992.5 1020.31  5004.3 1020.31  5004.8 1023.31  5013.2 1023.35
  5023.2 1024.77  5028.9 1028.24  5033.9 1027.89  5073.3 1033.05  5103.4 1035.88
  5176.9 1037.63  5203.6 1038.40  5223.6 1040.14  5243.7 1039.96  5263.7 1040.62
#Mann=5,-1,0
  4591.3    0.05       0  4924.0    0.12       0  4992.0    0.07       0
  5004.8    0.12       0  5176.9    0.05       0
Bank Sta=4992,5004.8
Exp/Cntr=0.3,0.1

Type RM Length L Ch R = 1,22888,486,486,486
BEGIN DESCRIPTION:
WATERS CREEK 43.0
END DESCRIPTION:
XS GIS Cut Line= 3
      2847405.70     10222803.10      2847545.50     10222642.00
      2847605.68     10222253.13
#Sta/Elev= 30
  4786.7 1044.22  4800.4 1043.01  4836.6 1038.07  4843.2 1038.31  4850.8 1036.68
  4871.7 1034.39  4879.3 1032.89  4885.9 1033.30  4892.6 1031.73  4906.8 1030.47
  4921.0 1027.73  4935.3 1026.06  4957.2 1024.93  5012.7 1020.14  5013.2 1017.14
  5025.0 1017.14  5025.5 1020.14  5034.1 1025.41  5049.5 1027.60  5059.6 1031.18
  5079.8 1032.80  5165.3 1035.03  5191.1 1036.59  5211.4 1036.90  5228.3 1036.18
  5262.0 1037.98  5296.4 1037.97  5342.9 1039.33  5373.3 1041.10  5393.5 1044.13
#Mann=3,-1,0
  4786.7    0.05       0  5012.7    0.05       0  5025.5    0.05       0
Bank Sta=5012.7,5025.5
Exp/Cntr=0.3,0.1

Type RM Length L Ch R = 1,22402,498,498,498
BEGIN DESCRIPTION:
WATERS CREEK 42.0
END DESCRIPTION:
XS GIS Cut Line= 3
      2847755.72     10223003.09      2847945.50     10222895.00
      2848555.71     10222353.09
#Sta/Elev= 30
  4781.6 1039.63  4812.6 1037.67  4875.9 1032.99  4890.1 1030.23  4950.9 1025.55
  4965.7 1021.79  4971.8 1016.10  4972.3 1013.10  4984.2 1013.10  4984.7 1016.10
  5022.9 1019.41  5057.2 1027.82  5114.9 1033.15  5150.0 1034.26  5221.1 1033.46
  5284.6 1035.43  5292.1 1033.47  5298.8 1035.16  5306.4 1033.24  5320.6 1032.60
  5327.3 1033.92  5334.6 1031.45  5341.5 1033.45  5348.2 1032.42  5376.6 1038.52
  5476.1 1046.52  5617.5 1062.71  5702.8 1074.56  5766.3 1079.30  5816.1 1084.95
#Mann=6,-1,0
  4781.6    0.05       0  4812.6    0.12       0  4890.1    0.05       0
  4971.8    0.05       0  4984.7    0.05       0  5057.2    0.12       0
Bank Sta=4971.8,4984.7
Exp/Cntr=0.3,0.1

Type RM Length L Ch R = 1,21904,459,459,459
BEGIN DESCRIPTION:
Mapping XS bec85ab0
END DESCRIPTION:
XS GIS Cut Line= 4
      2847667.90     10223212.52      2848157.43     10223207.31
      2848464.72     10223103.15      2848791.78     10222853.96
#Sta/Elev= 30
  4279.3 1047.99  4527.1 1031.26  4693.0 1026.86  4788.1 1027.03  4946.5 1022.89
  5008.9 1013.99  5009.4 1010.99  5021.3 1010.99  5021.8 1013.99  5041.5 1018.46
  5052.1 1022.20  5072.9 1024.97  5083.8 1030.08  5098.8 1033.34  5107.5 1036.16
  5122.1 1037.53  5227.2 1043.48  5386.1 1053.85  5408.8 1056.61  5415.1 1058.43
  5421.4 1057.99  5429.7 1059.98  5436.0 1059.75  5458.7 1063.47  5465.0 1063.43
  5479.6 1066.52  5485.8 1065.67  5494.1 1067.34  5500.4 1066.71  5504.5 1068.65
#Mann=5,-1,0
  4279.3    0.05       0  5008.9    0.05       0  5021.8    0.05       0
  5098.8    0.12       0  5227.2    0.05       0
Bank Sta=5008.9,5021.8
Exp/Cntr=0.3,0.1

Type RM Length L Ch R = 1,21445,476,476,476
BEGIN DESCRIPTION:
WATERS CREEK 40.0
END DESCRIPTION:
XS GIS Cut Line= 3
      2848005.68     10223603.11      2848195.50     10223514.00
      2848805.67     10223703.11
#Sta/Elev= 30
  4790.3 1037.59  4812.4 1036.02  4834.5 1031.15  4856.6 1028.28  4924.1 1024.23
  4933.9 1021.44  4941.4 1016.80  4946.9 1015.26  4969.7 1021.00  4987.0 1015.35
  4992.5 1016.52  4997.3 1013.84  5008.4 1012.74  5008.9 1009.74  5020.9 1009.74
  5021.4 1012.74  5080.1 1015.78  5104.9 1015.50  5199.1 1018.91  5253.5 1022.84
  5351.3 1032.84  5454.3 1037.78  5488.4 1043.35  5524.7 1051.39  5552.1 1061.06
  5576.0 1066.39  5617.3 1081.82  5622.5 1082.59  5628.3 1085.67  5638.8 1086.56
#Mann=4,-1,0
  4790.3    0.05       0  5008.4    0.05       0  5021.4    0.05       0
  5488.4    0.12       0
Bank Sta=5008.4,5021.4
Exp/Cntr=0.3,0.1

Type RM Length L Ch R = 1,20969,513,513,513
BEGIN DESCRIPTION:
WATERS CREEK 39.0
END DESCRIPTION:
XS GIS Cut Line= 3
      2848005.67     10223703.11      2848389.25     10223907.00
      2848705.65     10224053.10
#Sta/Elev= 30
  4565.6 1036.34  4678.0 1026.59  4705.6 1025.87  4721.9 1023.20  4826.1 1019.58
  4892.1 1014.13  4985.7 1010.23  4988.6 1008.20  4989.1 1005.20  5001.1 1005.20
  5001.6 1008.20  5002.1 1010.54  5007.6 1010.15  5018.1 1014.84  5025.1 1020.61
  5028.5 1019.39  5030.6 1018.64  5040.1 1022.95  5048.0 1024.21  5053.5 1022.49
  5062.2 1025.04  5122.3 1026.03  5196.7 1031.85  5219.6 1037.60  5237.0 1045.14
  5242.5 1045.93  5249.4 1050.98  5265.5 1057.37  5311.4 1073.31  5348.5 1082.50
#Mann=4,-1,0
  4565.6    0.05       0  4988.6    0.03       0  5001.6    0.05       0
  5028.5    0.12       0
Bank Sta=4988.6,5001.6
Exp/Cntr=0.3,0.1