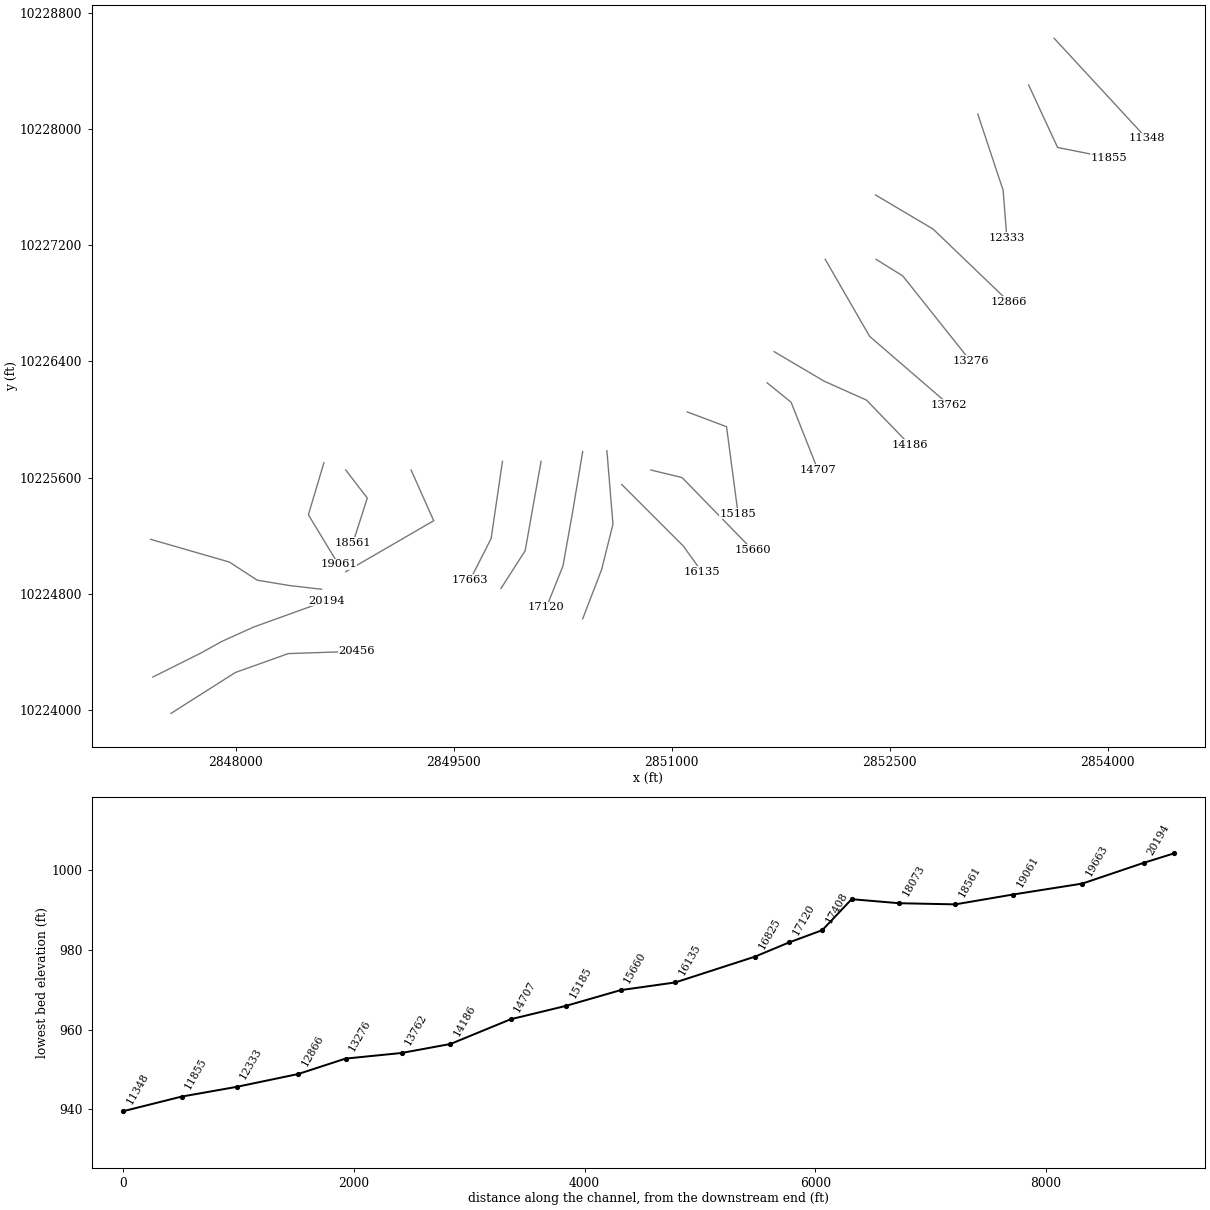
HEC-RAS study WATERS CREEK.prj: WATERS CREEK Base Level Engineering

--- WATERS CREEK.g01 (geometry) --- (continued)

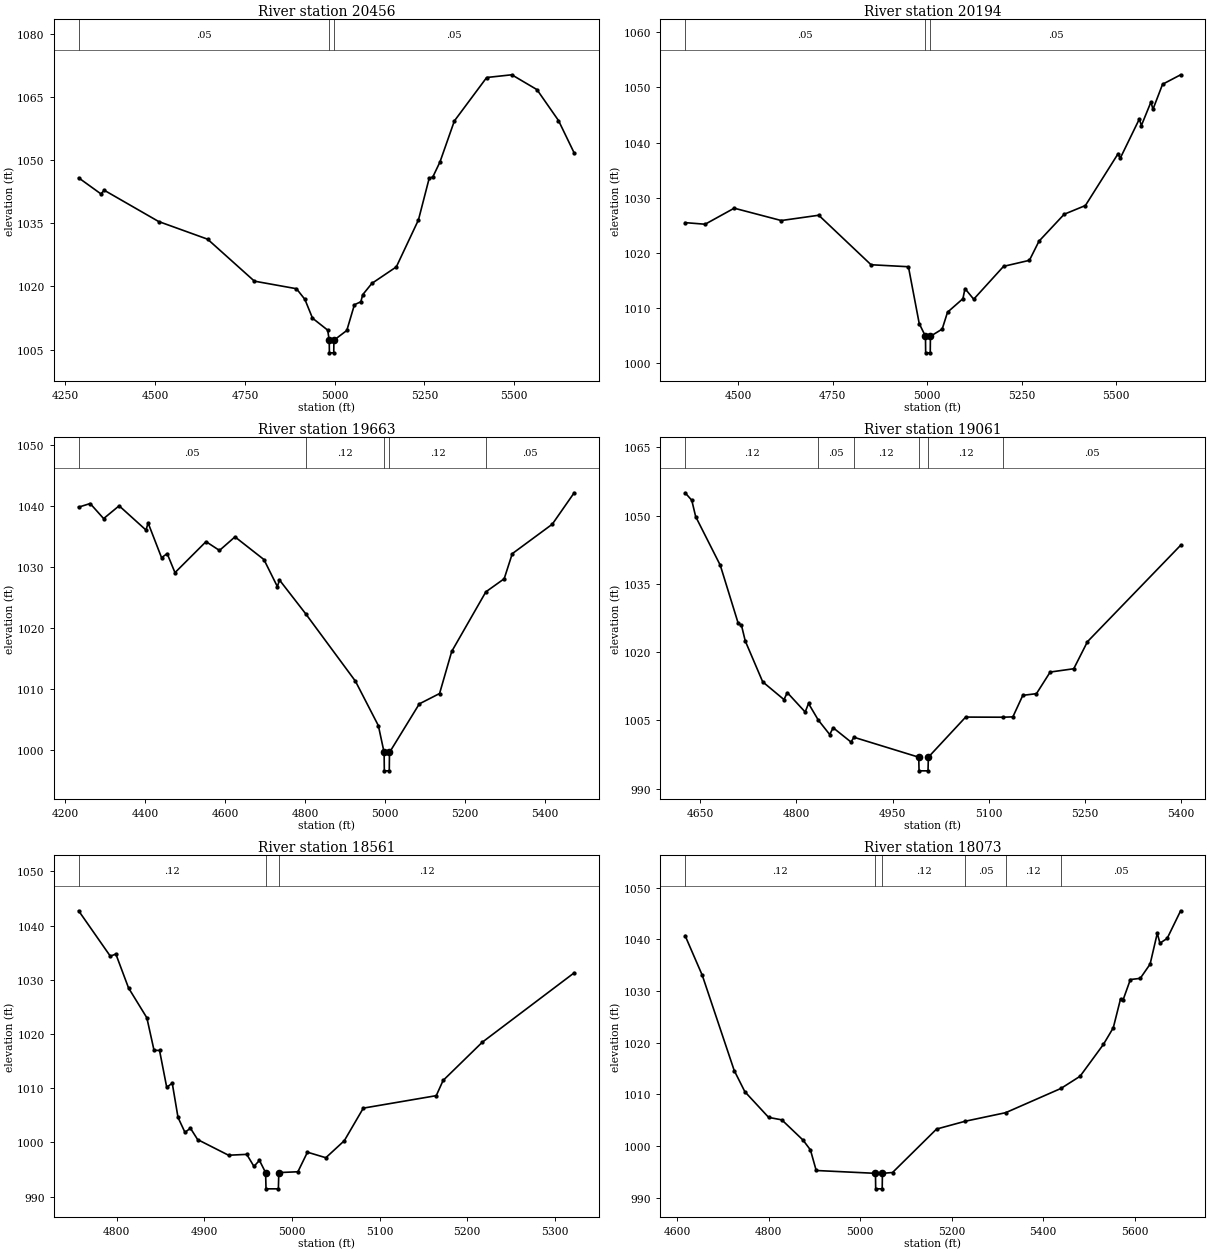
Type RM Length L Ch R = 1,20456,262,262,262
BEGIN DESCRIPTION:
Mapping XS 025d1710
END DESCRIPTION:
XS GIS Cut Line= 4
      2847553.25     10223978.14      2847995.97     10224259.40
      2848360.56     10224389.61      2848829.35     10224405.23
#Sta/Elev= 30
  4286.6 1045.84  4348.7 1042.02  4357.9 1042.89  4509.5 1035.45  4645.9 1031.25
  4776.3 1021.27  4893.5 1019.47  4917.0 1016.94  4938.2 1012.47  4980.5 1009.62
  4984.8 1007.22  4985.3 1004.22  4997.4 1004.22  4997.9 1007.22  5033.8 1009.54
  5055.0 1015.66  5072.9 1016.37  5078.2 1018.06  5103.7 1020.74  5171.8 1024.66
  5233.4 1035.83  5263.4 1045.75  5273.4 1046.04  5293.4 1049.62  5333.5 1059.37
  5423.5 1069.70  5493.5 1070.35  5563.6 1066.82  5623.6 1059.47  5667.3 1051.76
#Mann=3,-1,0
  4286.6    0.05       0  4984.8    0.03       0  4997.9    0.05       0
Bank Sta=4984.8,4997.9
Exp/Cntr=0.3,0.1

Type RM Length L Ch R = 1,20194,531,531,531
BEGIN DESCRIPTION:
Mapping XS 5bb9fafe
END DESCRIPTION:
XS GIS Cut Line= 5
      2847428.25     10224228.14      2847761.60     10224394.81
      2847902.22     10224472.94      2848120.97     10224571.90
      2848626.14     10224754.18
#Sta/Elev= 30
  4359.3 1025.47  4412.3 1025.18  4489.2 1028.09  4613.6 1025.85  4712.8 1026.81
  4851.1 1017.83  4950.0 1017.47  4978.6 1007.15  4995.1 1004.85  4995.6 1001.85
  5007.7 1001.85  5008.2 1004.85  5039.3 1006.16  5053.4 1009.22  5094.1 1011.67
  5099.6 1013.50  5122.7 1011.58  5201.7 1017.54  5270.0 1018.63  5295.3 1022.10
  5362.0 1026.99  5418.1 1028.57  5504.8 1038.00  5510.1 1037.13  5560.8 1044.27
  5566.1 1043.07  5591.5 1047.35  5596.8 1046.03  5622.2 1050.57  5670.0 1052.29
#Mann=3,-1,0
  4359.3    0.05       0  4995.1    0.03       0  5008.2    0.05       0
Bank Sta=4995.1,5008.2
Exp/Cntr=0.3,0.1

Type RM Length L Ch R = 1,19663,602,602,602
BEGIN DESCRIPTION:
Mapping XS 6ce7cfbb
END DESCRIPTION:
XS GIS Cut Line= 5
      2847412.68     10225176.05      2847954.31     10225019.81
      2848147.01     10224894.81      2848365.76     10224858.36
      2848589.67     10224832.32
#Sta/Elev= 30
  4233.0 1039.77  4261.9 1040.36  4295.6 1037.90  4334.4 1039.99  4401.7 1036.02
  4406.9 1037.19  4440.6 1031.51  4454.7 1032.17  4474.2 1029.06  4551.9 1034.13
  4585.6 1032.69  4624.4 1034.91  4696.9 1031.20  4730.6 1026.77  4735.8 1027.86
  4801.0 1022.37  4926.0 1011.31  4983.4 1004.04  4997.8  999.65  4998.3  996.65
  5010.7  996.65  5011.2  999.65  5085.9 1007.60  5136.6 1009.29  5167.0 1016.17
  5252.5 1025.92  5298.4 1028.06  5318.6 1032.16  5418.8 1036.98  5473.6 1042.12
#Mann=5,-1,0
  4233.0    0.05       0  4801.0    0.12       0  4997.8    0.07       0
  5011.2    0.12       0  5252.5    0.05       0
Bank Sta=4997.8,5011.2
Exp/Cntr=0.3,0.1

Type RM Length L Ch R = 1,19061,500,500,500
BEGIN DESCRIPTION:
WATERS CREEK 35.0
END DESCRIPTION:
XS GIS Cut Line= 3
      2848605.67     10225703.08      2848498.75     10225345.00
      2848705.67     10225003.14
#Sta/Elev= 30
  4626.3 1055.04  4636.7 1053.40  4642.8 1049.80  4681.2 1039.10  4709.1 1026.37
  4714.3 1025.88  4720.2 1022.45  4747.4 1013.47  4780.6 1009.57  4785.8 1011.10
  4813.7 1006.83  4818.9 1008.71  4834.1 1005.07  4852.0 1001.88  4857.3 1003.38
  4885.2 1000.23  4889.8 1001.28  4990.9  996.90  4991.4  993.90  5005.4  993.90
  5005.9  996.90  5064.1 1005.72  5122.9 1005.69  5137.8 1005.77  5153.3 1010.50
  5174.6 1010.87  5196.0 1015.62  5232.8 1016.35  5254.2 1022.30  5399.6 1043.50
#Mann=6,-1,0
  4626.3    0.12       0  4834.1    0.05       0  4889.8    0.12       0
  4990.9    0.07       0  5005.9    0.12       0  5122.9    0.05       0
Bank Sta=4990.9,5005.9
Exp/Cntr=0.3,0.1

Type RM Length L Ch R = 1,18561,488,488,488
BEGIN DESCRIPTION:
WATERS CREEK 34.0
END DESCRIPTION:
XS GIS Cut Line= 3
      2848755.71     10225653.07      2848904.25     10225460.00
      2848805.69     10225153.14
#Sta/Elev= 30
  4756.4 1042.73  4792.6 1034.35  4798.9 1034.75  4813.4 1028.49  4834.3 1022.99
  4842.5 1016.99  4848.8 1016.96  4857.0 1010.16  4863.3 1010.93  4869.9 1004.60
  4877.8 1001.86  4884.1 1002.61  4892.3 1000.52  4927.6  997.63  4948.4  997.79
  4956.6  995.57  4962.9  996.68  4969.9  994.43  4970.4  991.43  4984.5  991.43
  4985.0  994.43  5006.8  994.58  5017.7  998.19  5038.7  997.17  5059.8 1000.31
  5081.5 1006.32  5164.8 1008.62  5172.6 1011.42  5217.3 1018.47  5322.3 1031.28
#Mann=3,-1,0
  4756.4    0.12       0  4969.9    0.07       0  4985.0    0.12       0
Bank Sta=4969.9,4985
Exp/Cntr=0.3,0.1

Type RM Length L Ch R = 1,18073,410,410,410
BEGIN DESCRIPTION:
WATERS CREEK 33.0
END DESCRIPTION:
XS GIS Cut Line= 3
      2849205.69     10225653.11      2849361.25     10225304.00
      2848755.67     10224953.10
#Sta/Elev= 30
  4617.8 1040.73  4655.4 1033.03  4725.1 1014.61  4748.3 1010.52  4800.2 1005.55
  4829.0 1005.07  4875.4 1001.15  4891.5  999.25  4904.1  995.27  5033.5  994.72
  5034.0  991.72  5048.2  991.72  5048.7  994.72  5070.8  994.88  5166.9 1003.29
  5229.3 1004.80  5317.8 1006.46  5438.7 1011.16  5480.3 1013.51  5531.3 1019.68
  5552.8 1022.89  5568.6 1028.46  5574.4 1028.33  5590.1 1032.23  5611.7 1032.46
  5633.2 1035.21  5648.9 1041.19  5654.7 1039.27  5670.5 1040.19  5699.9 1045.54
#Mann=6,-1,0
  4617.8    0.12       0  5033.5    0.07       0  5048.7    0.12       0
  5229.3    0.05       0  5317.8    0.12       0  5438.7    0.05       0
Bank Sta=5033.5,5048.7
Exp/Cntr=0.3,0.1

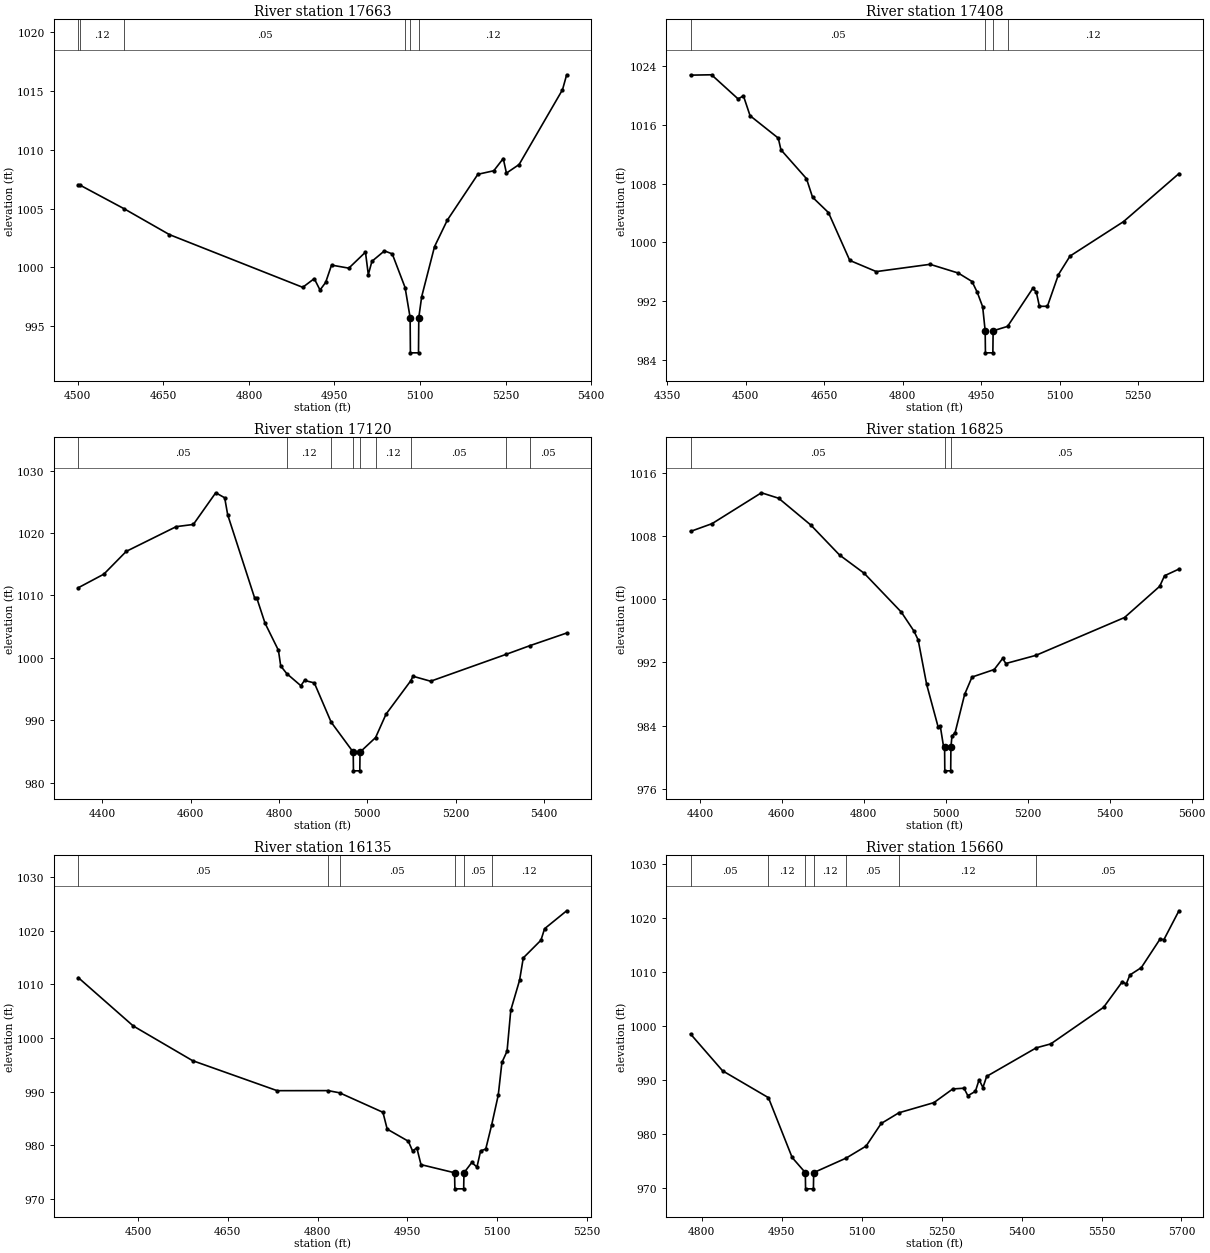
Type RM Length L Ch R = 1,17663,255,255,255
BEGIN DESCRIPTION:
Mapping XS 1c1c9ea6
END DESCRIPTION:
XS GIS Cut Line= 3
      2849834.51     10225712.51      2849756.39     10225181.27
      2849611.46     10224896.59
#Sta/Elev= 30
  4500.8 1007.02  4503.4 1007.00  4581.2 1004.98  4660.7 1002.78  4894.4  998.30
  4914.6  999.04  4924.7  998.07  4934.6  998.72  4944.9 1000.19  4975.2  999.93
  5004.4 1001.29  5009.4  999.38  5015.7 1000.51  5037.7 1001.40  5051.4 1001.14
  5073.9  998.28  5082.7  995.73  5083.2  992.73  5097.4  992.73  5097.9  995.73
  5103.0  997.51  5125.5 1001.76  5147.9 1004.01  5201.5 1007.91  5229.4 1008.21
  5246.0 1009.25  5251.6 1008.01  5273.8 1008.74  5349.9 1015.10  5357.2 1016.37
#Mann=6,-1,0
  4500.8    0.05       0  4503.4    0.12       0  4581.2    0.05       0
  5073.9    0.12       0  5082.7    0.03       0  5097.9    0.12       0
Bank Sta=5082.7,5097.9
Exp/Cntr=0.3,0.1

Type RM Length L Ch R = 1,17408,288,288,288
BEGIN DESCRIPTION:
Mapping XS 8f609d33
END DESCRIPTION:
XS GIS Cut Line= 3
      2850100.15     10225712.56      2849990.76     10225097.94
      2849824.29     10224837.83
#Sta/Elev= 30
  4395.0 1022.75  4435.1 1022.80  4485.9 1019.51  4496.0 1019.94  4508.7 1017.23
  4562.6 1014.18  4567.7 1012.59  4616.5 1008.66  4628.1 1006.13  4658.5 1004.04
  4699.2  997.53  4749.9  996.01  4852.6  997.00  4906.5  995.81  4932.8  994.66
  4942.9  993.17  4953.1  991.22  4957.9  987.95  4958.4  984.95  4972.6  984.95
  4973.1  987.95  5000.7  988.55  5048.8  993.72  5055.6  993.24  5061.5  991.28
  5076.8  991.29  5097.9  995.60  5120.0  998.12  5222.2 1002.81  5328.1 1009.35
#Mann=4,-1,0
  4395.0    0.05       0  4957.9    0.03       0  4973.1    0.05       0
  5000.7    0.12       0
Bank Sta=4957.9,4973.1
Exp/Cntr=0.3,0.1

Type RM Length L Ch R = 1,17120,295,295,295
BEGIN DESCRIPTION:
Mapping XS b7f4389b
END DESCRIPTION:
XS GIS Cut Line= 4
      2850386.59     10225780.19      2850318.89     10225373.98
      2850251.18     10224993.77      2850136.76     10224707.71
#Sta/Elev= 30
  4345.3 1011.23  4403.2 1013.41  4453.9 1017.06  4567.1 1021.03  4605.9 1021.38
  4656.6 1026.46  4676.9 1025.66  4683.7 1022.93  4744.5 1009.64  4749.6 1009.58
  4768.2 1005.56  4798.6 1001.20  4803.8  998.69  4817.5  997.46  4849.4  995.52
  4857.7  996.37  4879.9  995.97  4918.0  989.68  4968.0  984.87  4968.5  981.87
  4982.9  981.87  4983.4  984.87  5018.6  987.20  5042.4  990.97  5098.3  996.31
  5103.3  997.04  5143.3  996.24  5314.6 1000.56  5368.4 1001.95  5451.4 1003.97
#Mann=9,-1,0
  4345.3    0.05       0  4817.5    0.12       0  4918.0    0.05       0
  4968.0    0.03       0  4983.4    0.05       0  5018.6    0.12       0
  5098.3    0.05       0  5314.6    0.12       0  5368.4    0.05       0
Bank Sta=4968,4983.4
Exp/Cntr=0.3,0.1

Type RM Length L Ch R = 1,16825,690,690,690
BEGIN DESCRIPTION:
Mapping XS 04e0af9d
END DESCRIPTION:
XS GIS Cut Line= 4
      2850553.27     10225785.39      2850594.93     10225280.23
      2850516.81     10224967.73      2850386.60     10224629.20
#Sta/Elev= 30
  4377.3 1008.56  4429.8 1009.54  4550.2 1013.44  4592.3 1012.75  4670.6 1009.37
  4740.8 1005.58  4801.0 1003.27  4891.5  998.37  4922.4  995.97  4932.7  994.85
  4953.4  989.23  4981.6  983.82  4986.8  983.92  4994.6  981.39  4997.2  981.31
  4997.7  978.31  5012.1  978.31  5012.6  981.31  5015.2  982.70  5022.9  983.15
  5046.1  987.97  5064.1  990.16  5118.3  991.11  5138.9  992.51  5146.6  991.87
  5220.0  992.90  5436.2  997.68  5522.0 1001.62  5533.9 1002.96  5569.0 1003.80
#Mann=3,-1,0
  4377.3    0.05       0  4997.2    0.05       0  5012.6    0.05       0
Bank Sta=4997.2,5012.6
Exp/Cntr=0.3,0.1

Type RM Length L Ch R = 1,16135,475,475,475
BEGIN DESCRIPTION:
WATERS CREEK 29.0
END DESCRIPTION:
XS GIS Cut Line= 3
      2850655.70     10225553.09      2851080.00     10225129.00
      2851205.70     10224953.09
#Sta/Elev= 30
  4400.1 1011.28  4492.0 1002.25  4591.0  995.78  4732.4  990.17  4817.5  990.18
  4836.8  989.77  4909.2  986.13  4916.3  982.99  4951.6  980.73  4958.7  978.92
  4965.8  979.49  4972.8  976.36  5028.9  974.84  5029.4  971.84  5044.1  971.84
  5044.6  974.84  5057.7  976.76  5066.3  975.91  5072.4  978.92  5081.0  979.28
  5090.9  983.78  5101.9  989.35  5108.0  995.45  5116.6  997.54  5122.8 1005.18
  5137.5 1010.78  5143.7 1014.96  5173.2 1018.26  5179.3 1020.41  5216.2 1023.76
#Mann=6,-1,0
  4400.1    0.05       0  4817.5    0.12       0  4836.8    0.05       0
  5028.9    0.05       0  5044.6    0.05       0  5090.9    0.12       0
Bank Sta=5028.9,5044.6
Exp/Cntr=0.3,0.1

Type RM Length L Ch R = 1,15660,475,475,475
BEGIN DESCRIPTION:
WATERS CREEK 28.0
END DESCRIPTION:
XS GIS Cut Line= 3
      2850855.73     10225653.10      2851070.50     10225601.00
      2851555.69     10225103.11
#Sta/Elev= 30
  4779.0  998.55  4839.1  991.74  4925.1  986.77  4969.6  975.70  4994.3  972.90
  4994.8  969.90  5009.5  969.90  5010.0  972.90  5071.1  975.60  5108.3  977.81
  5136.6  981.99  5169.8  983.97  5235.5  985.85  5270.9  988.38  5292.0  988.52
  5299.2  987.13  5313.4  987.94  5320.3  990.09  5327.5  988.64  5334.5  990.71
  5427.5  995.99  5454.8  996.72  5553.8 1003.48  5589.1 1008.24  5596.3 1007.79
  5603.2 1009.47  5624.6 1010.83  5659.8 1016.12  5667.0 1016.01  5695.2 1021.35
#Mann=7,-1,0
  4779.0    0.05       0  4925.1    0.12       0  4994.3    0.07       0
  5010.0    0.12       0  5071.1    0.05       0  5169.8    0.12       0
  5427.5    0.05       0
Bank Sta=4994.3,5010
Exp/Cntr=0.3,0.1

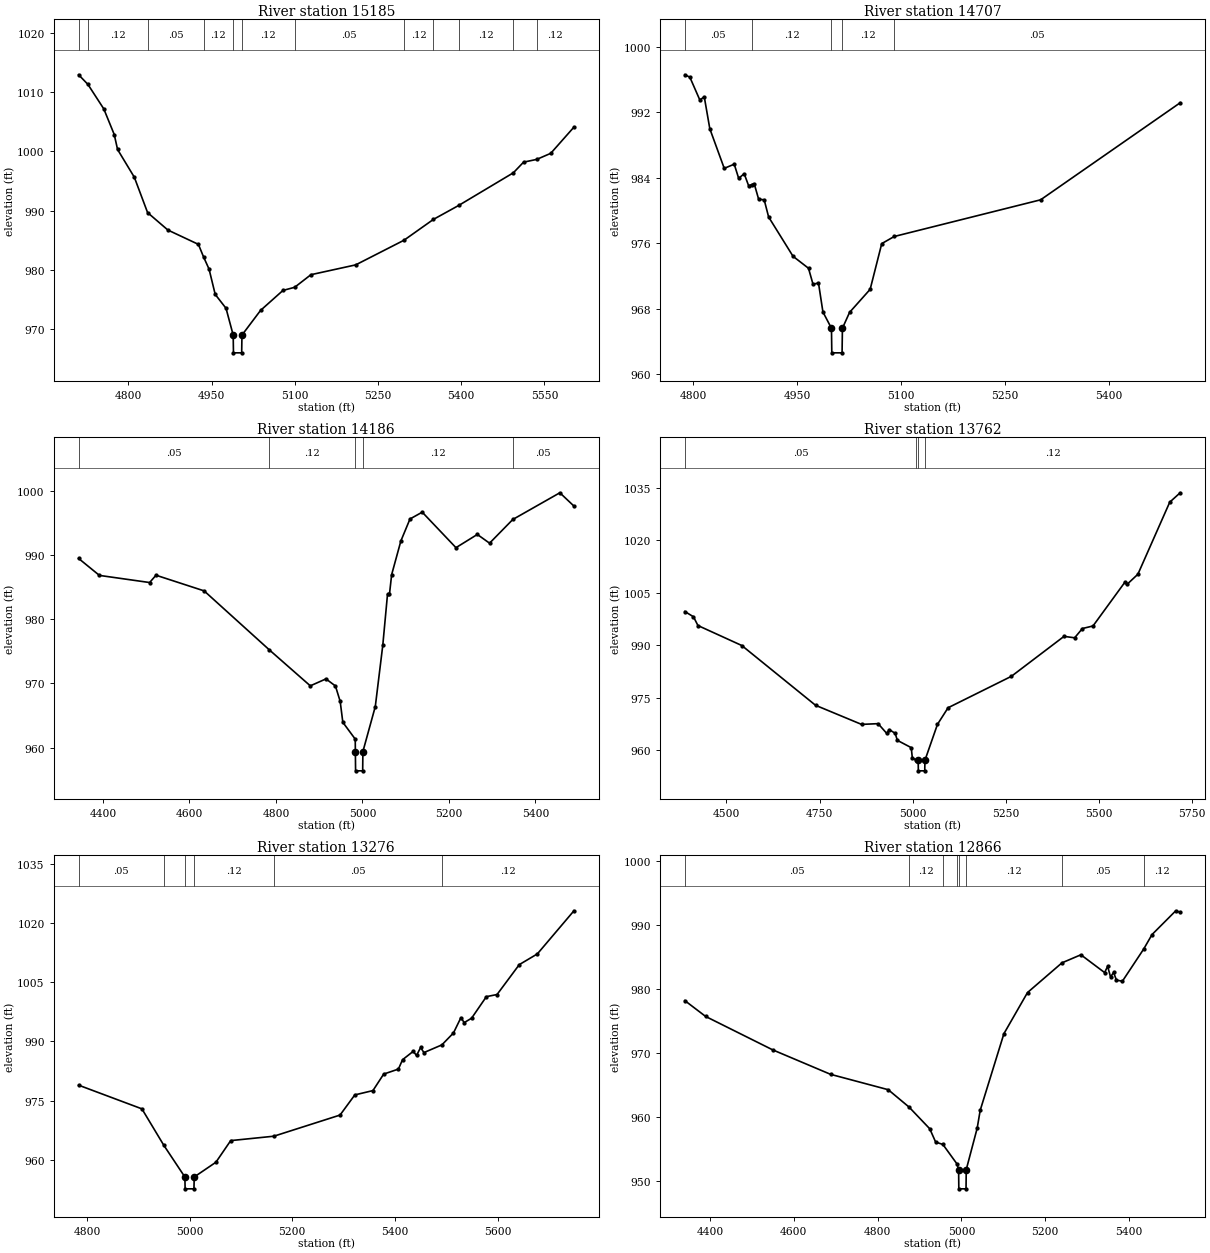
Type RM Length L Ch R = 1,15185,478,478,478
BEGIN DESCRIPTION:
WATERS CREEK 27.0
END DESCRIPTION:
XS GIS Cut Line= 3
      2851105.65     10226053.13      2851376.75     10225951.00
      2851455.69     10225353.09
#Sta/Elev= 30
  4710.3 1012.95  4727.0 1011.33  4755.7 1007.18  4774.5 1002.85  4780.5 1000.32
  4810.7  995.63  4834.6  989.65  4871.2  986.70  4926.2  984.28  4935.7  982.11
  4945.4  980.10  4956.5  975.82  4976.0  973.47  4988.9  968.94  4989.4  965.94
  5004.2  965.94  5004.7  968.94  5038.2  973.11  5078.6  976.49  5099.7  977.02
  5129.0  979.15  5209.7  980.81  5296.8  984.98  5349.8  988.50  5395.4  990.86
  5493.9  996.38  5512.3  998.18  5535.9  998.64  5561.3  999.67  5603.1 1004.10
#Mann=12,-1,0
  4710.3    0.05       0  4727.0    0.12       0  4834.6    0.05       0
  4935.7    0.12       0  4988.9    0.07       0  5004.7    0.12       0
  5099.7    0.05       0  5296.8    0.12       0  5349.8    0.05       0
  5395.4    0.12       0  5493.9    0.05       0  5535.9    0.12       0
Bank Sta=4988.9,5004.7
Exp/Cntr=0.3,0.1

Type RM Length L Ch R = 1,14707,521,521,521
BEGIN DESCRIPTION:
WATERS CREEK 26.0
END DESCRIPTION:
XS GIS Cut Line= 3
      2851655.65     10226253.14      2851820.50     10226120.00
      2852005.69     10225653.09
#Sta/Elev= 30
  4788.1  996.55  4795.3  996.26  4809.7  993.47  4816.1  993.86  4824.1  989.96
  4844.9  985.12  4859.3  985.63  4865.7  983.91  4873.7  984.46  4880.1  982.99
  4884.7  983.14  4888.1  983.25  4894.5  981.35  4902.5  981.28  4908.9  979.18
  4944.1  974.38  4966.4  972.92  4972.9  970.97  4980.8  971.12  4987.2  967.58
  4999.5  965.59  5000.0  962.59  5014.8  962.59  5015.3  965.59  5025.6  967.53
  5055.3  970.35  5072.0  975.93  5090.0  976.80  5301.1  981.28  5502.3  993.13
#Mann=5,-1,0
  4788.1    0.05       0  4884.7    0.12       0  4999.5    0.07       0
  5015.3    0.12       0  5090.0    0.05       0
Bank Sta=4999.5,5015.3
Exp/Cntr=0.3,0.1

Type RM Length L Ch R = 1,14186,424,424,424
BEGIN DESCRIPTION:
Mapping XS 271bf3a6
END DESCRIPTION:
XS GIS Cut Line= 4
      2851704.28     10226467.74      2852048.06     10226264.61
      2852339.72     10226134.40      2852636.12     10225827.60
#Sta/Elev= 30
  4343.7  989.47  4391.8  986.83  4507.9  985.72  4522.6  986.86  4633.9  984.42
  4784.7  975.23  4879.4  969.63  4915.6  970.71  4937.5  969.61  4948.5  967.21
  4954.6  963.95  4983.3  961.33  4983.6  959.39  4984.1  956.39  5000.5  956.39
  5001.0  959.39  5029.7  966.41  5047.0  975.95  5057.9  983.87  5062.4  983.87
  5067.5  986.95  5088.8  992.19  5109.9  995.62  5138.2  996.68  5216.2  991.15
  5265.6  993.21  5293.9  991.85  5347.6  995.54  5456.4  999.70  5489.0  997.63
#Mann=5,-1,0
  4343.7    0.05       0  4784.7    0.12       0  4983.6    0.07       0
  5001.0    0.12       0  5347.6    0.05       0
Bank Sta=4983.6,5001
Exp/Cntr=0.3,0.1

Type RM Length L Ch R = 1,13762,486,486,486
BEGIN DESCRIPTION:
WATERS CREEK 24.0
END DESCRIPTION:
XS GIS Cut Line= 3
      2852055.67     10227103.13      2852361.25     10226573.00
      2852905.71     10226103.09
#Sta/Elev= 30
  4388.1  999.61  4411.2  998.12  4423.3  995.61  4541.1  989.91  4739.4  972.84
  4862.9  967.39  4907.5  967.60  4930.6  964.82  4937.6  965.89  4953.4  964.83
  4959.1  962.84  4996.5  960.75  4999.4  957.86  5009.7  957.21  5015.1  957.13
  5015.6  954.13  5032.8  954.13  5033.3  957.13  5067.0  967.41  5095.5  972.14
  5265.6  981.11  5407.1  992.52  5435.6  992.11  5456.5  994.76  5485.0  995.49
  5570.5 1007.96  5577.1 1007.43  5605.6 1010.26  5691.2 1030.83  5719.2 1033.51
#Mann=4,-1,0
  4388.1    0.05       0  5009.7    0.12       0  5015.1    0.03       0
  5033.3    0.12       0
Bank Sta=5015.1,5033.3
Exp/Cntr=0.3,0.1

Type RM Length L Ch R = 1,13276,410,410,410
BEGIN DESCRIPTION:
WATERS CREEK 23.0
END DESCRIPTION:
XS GIS Cut Line= 3
      2852405.72     10227103.09      2852589.25     10226989.00
      2853055.69     10226403.10
#Sta/Elev= 30
  4783.9  978.94  4907.2  972.95  4950.0  963.71  4990.9  955.72  4991.4  952.72
  5008.6  952.72  5009.1  955.72  5051.4  959.45  5080.2  964.92  5164.2  966.03
  5293.2  971.38  5322.0  976.48  5357.3  977.57  5378.2  981.74  5406.9  983.01
  5415.0  985.38  5435.8  987.50  5442.2  986.45  5450.2  988.47  5456.6  987.18
  5491.6  989.13  5514.2  992.15  5528.7  996.02  5535.1  994.76  5549.5  995.88
  5578.3 1001.33  5599.1 1001.87  5642.4 1009.43  5677.6 1012.14  5748.9 1023.05
#Mann=6,-1,0
  4783.9    0.05       0  4950.0    0.12       0  4990.9    0.07       0
  5009.1    0.12       0  5164.2    0.05       0  5491.6    0.12       0
Bank Sta=4990.9,5009.1
Exp/Cntr=0.3,0.1

Type RM Length L Ch R = 1,12866,533,533,533
BEGIN DESCRIPTION:
Mapping XS 5dcef5ed
END DESCRIPTION:
XS GIS Cut Line= 3
      2852402.24     10227545.85      2852798.06     10227311.48
      2853318.90     10226811.47
#Sta/Elev= 30
  4339.9  978.24  4389.5  975.77  4549.3  970.56  4687.7  966.73  4825.2  964.33
  4874.9  961.62  4924.3  958.23  4938.4  956.15  4955.7  955.78  4989.3  952.74
  4993.2  951.85  4993.7  948.85  5010.9  948.85  5011.4  951.85  5037.5  958.32
  5044.7  961.11  5101.3  973.08  5157.6  979.50  5239.8  984.14  5285.0  985.40
  5341.6  982.62  5348.8  983.59  5355.8  981.93  5363.0  982.64  5369.9  981.43
  5384.1  981.28  5434.8  986.29  5454.8  988.56  5511.4  992.27  5521.9  992.04
#Mann=8,-1,0
  4339.9    0.05       0  4874.9    0.12       0  4955.7    0.05       0
  4989.3    0.12       0  4993.2    0.07       0  5011.4    0.12       0
  5239.8    0.05       0  5434.8    0.12       0
Bank Sta=4993.2,5011.4
Exp/Cntr=0.3,0.1

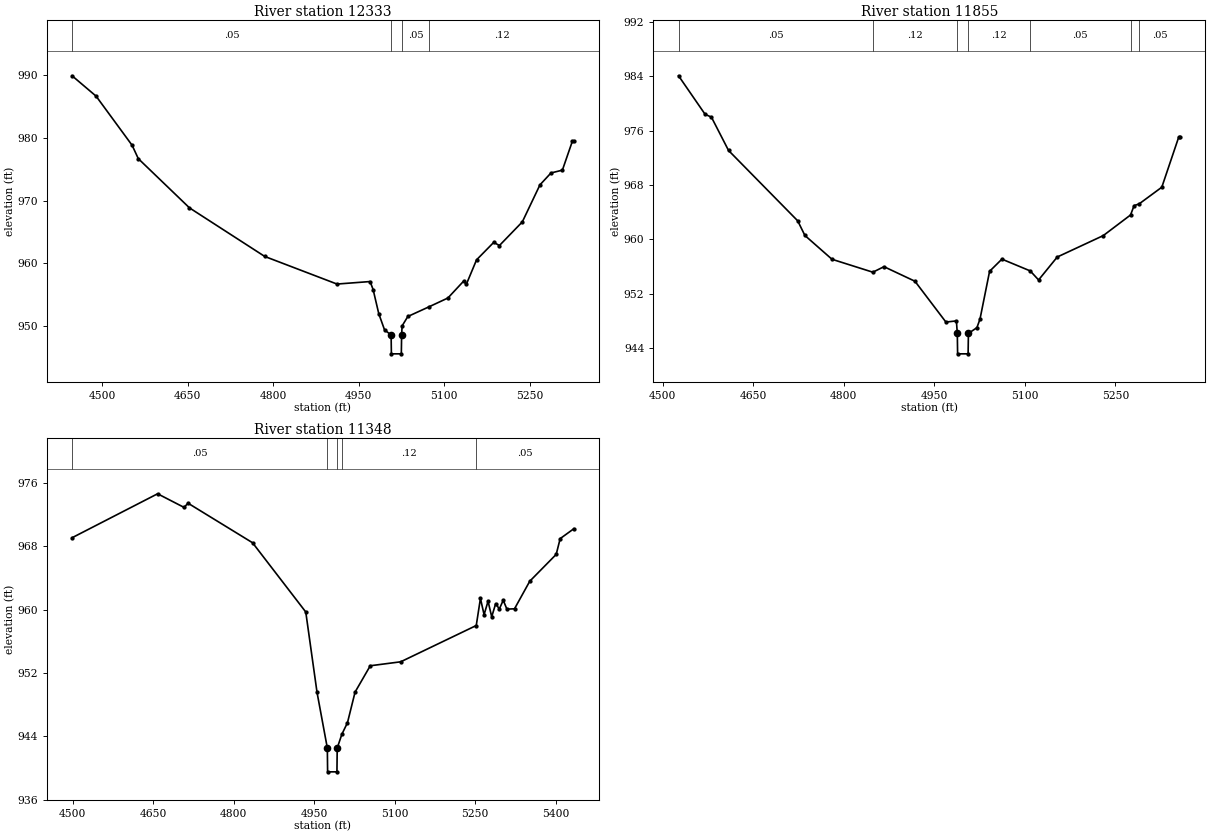
Type RM Length L Ch R = 1,12333,478,478,478
BEGIN DESCRIPTION:
WATERS CREEK 21.0
END DESCRIPTION:
XS GIS Cut Line= 3
      2853105.70     10228103.07      2853280.00     10227579.00
      2853305.68     10227253.11
#Sta/Elev= 30
  4447.7  989.86  4489.8  986.62  4553.0  978.79  4563.7  976.68  4653.4  968.85
  4785.3  961.12  4911.9  956.73  4969.9  957.13  4975.2  955.85  4985.1  952.01
  4995.2  949.44  5006.7  948.63  5007.2  945.63  5024.6  945.63  5025.1  948.63
  5026.0  950.08  5036.0  951.57  5073.8  953.14  5106.2  954.51  5133.6  957.18
  5138.7  956.73  5156.4  960.58  5186.5  963.36  5196.5  962.86  5236.6  966.62
  5267.5  972.51  5286.8  974.40  5306.8  974.85  5324.4  979.48  5326.9  979.48
#Mann=4,-1,0
  4447.7    0.05       0  5006.7    0.05       0  5025.1    0.05       0
  5073.8    0.12       0
Bank Sta=5006.7,5025.1
Exp/Cntr=0.3,0.1

Type RM Length L Ch R = 1,11855,507,507,507
BEGIN DESCRIPTION:
WATERS CREEK 20.0
END DESCRIPTION:
XS GIS Cut Line= 3
      2853455.70     10228303.07      2853655.00     10227873.00
      2854005.70     10227803.11
#Sta/Elev= 30
  4526.0  984.05  4570.0  978.39  4580.5  977.97  4608.9  973.07  4723.5  962.73
  4735.4  960.58  4780.3  957.08  4848.0  955.18  4866.5  955.99  4917.8  953.85
  4969.1  947.85  4986.5  948.02  4988.0  946.18  4988.5  943.18  5005.9  943.18
  5006.4  946.18  5020.5  947.03  5025.6  948.29  5041.5  955.31  5061.9  957.10
  5108.8  955.37  5122.7  954.04  5153.6  957.41  5229.9  960.56  5275.1  963.59
  5281.0  964.97  5289.2  965.21  5326.9  967.67  5355.0  975.05  5357.6  975.05
#Mann=7,-1,0
  4526.0    0.05       0  4848.0    0.12       0  4988.0    0.07       0
  5006.4    0.12       0  5108.8    0.05       0  5275.1    0.12       0
  5289.2    0.05       0
Bank Sta=4988,5006.4
Exp/Cntr=0.3,0.1

Type RM Length L Ch R = 1,11348,453,453,453
BEGIN DESCRIPTION:
Mapping XS 318703a5
END DESCRIPTION:
XS GIS Cut Line= 2
      2853631.39     10228623.98      2854266.08     10227937.26
#Sta/Elev= 30
  4499.1  969.06  4658.5  974.61  4707.8  972.89  4715.2  973.42  4835.4  968.43
  4934.6  959.69  4955.6  949.54  4974.8  942.51  4975.3  939.51  4992.7  939.51
  4993.2  942.51  5001.8  944.24  5012.3  945.71  5026.5  949.58  5054.8  952.90
  5111.5  953.40  5252.3  957.98  5260.1  961.40  5266.9  959.35  5274.3  961.05
  5281.1  959.08  5288.5  960.74  5295.3  960.07  5302.6  961.17  5309.4  960.05
  5323.6  960.09  5352.0  963.57  5401.3  966.96  5408.7  968.95  5434.2  970.20
#Mann=5,-1,0
  4499.1    0.05       0  4974.8    0.05       0  4993.2    0.05       0
  5001.8    0.12       0  5252.3    0.05       0
Bank Sta=4974.8,4993.2
Exp/Cntr=0.3,0.1