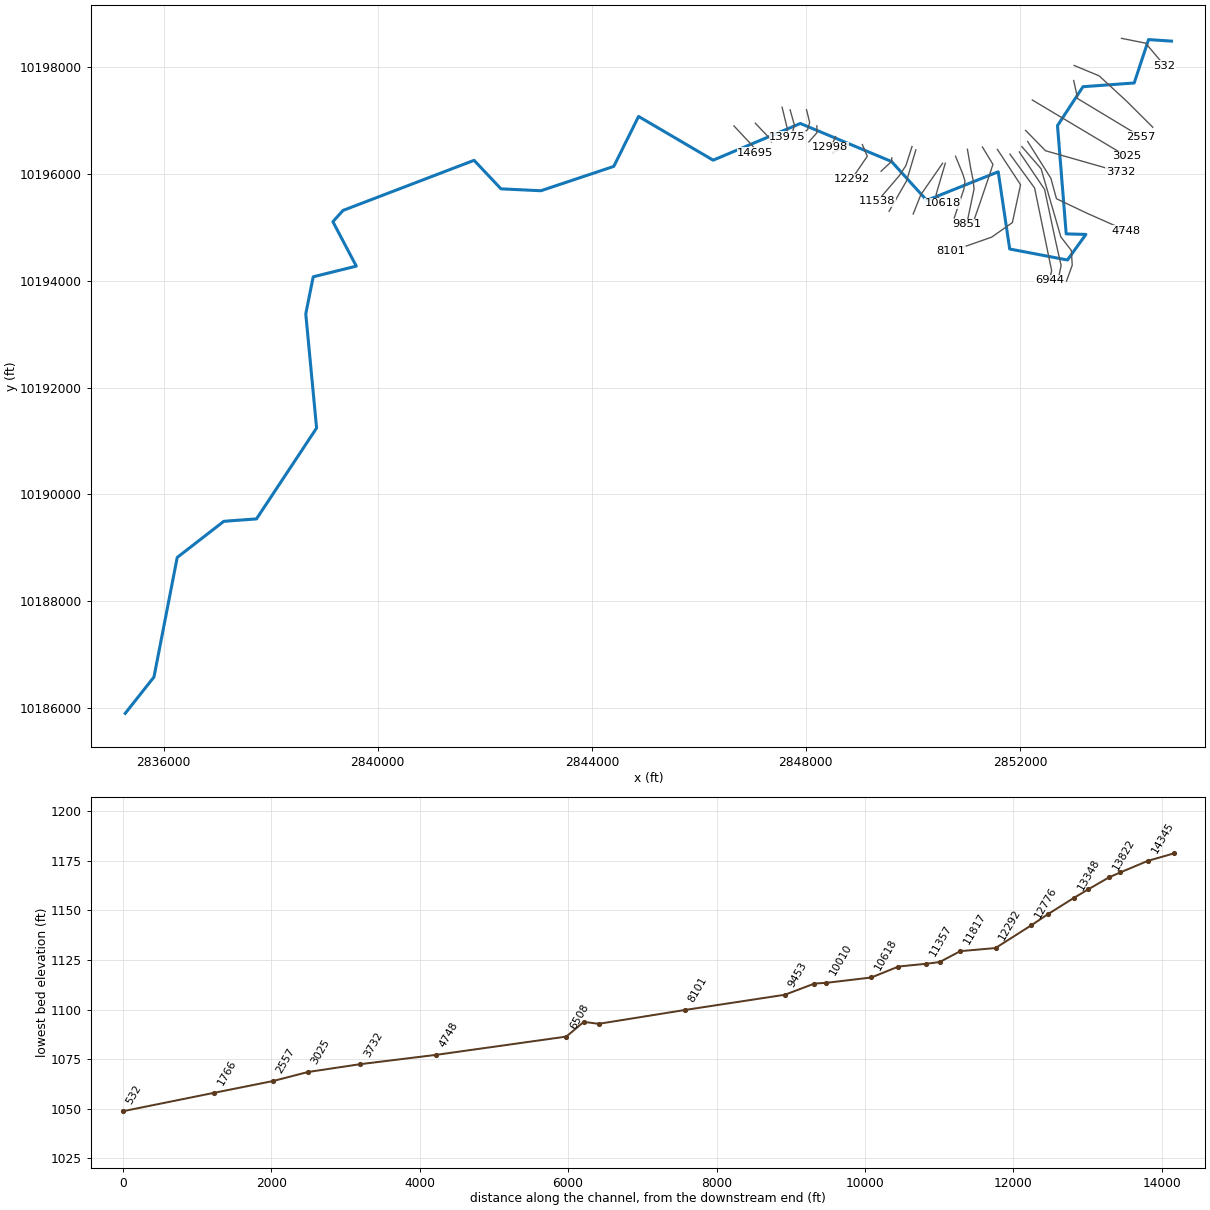
--- WOLF HOLLOW CREEK.prj (project) ---

Proj Title=WOLF HOLLOW CREEK Base Level Engineering
Current Plan=p01
Default Exp/Contr=0.3,0.1
English Units
Geom File=g01
Flow File=f01
Plan File=p01
Y Axis Title=Elevation
X Axis Title(PF)=Main Channel Distance
X Axis Title(XS)=Station
BEGIN DESCRIPTION:
WOLF HOLLOW CREEK
END DESCRIPTION:
DSS Export Rating Curves= 0
DSS Export Rating Curve Sorted= 0
DSS Export Volume Flow Curves= 0
DXF OffsetX= 0
DXF OffsetY= 0
DXF ScaleX= 1
DXF ScaleY= 10

--- WOLF HOLLOW CREEK.p01 (plan) ---

Plan Title=Multiple Run
Short Identifier=Multiple
Geom File=g01
Flow File=f01
Subcritical Flow
K Sum by GR= 0
Std Step Tol= 0.01
Critical Tol= 0.01
Num of Std Step Trials= 20
Max Error Tol= 0.3
Flow Tol Ratio= 0.001
Split Flow NTrial= 30
Split Flow Tol= 0.02
Split Flow Ratio= 0.02
Log Output Level= 0
Friction Slope Method= 1
Unsteady Friction Slope Method= 2
Unsteady Bridges Friction Slope Method= 1
Parabolic Critical Depth
Global Vel Dist=  1 , 1 , 1
Global Log Level= 0
CheckData=True
Encroach Param= -1, 0, 0, 0
BEGIN DESCRIPTION:
Multiple Run
END DESCRIPTION:

--- WOLF HOLLOW CREEK.f01 (steady flow) ---

Flow Title=Multiple
Program Version=4.10
Number of Profiles= 7
Profile Names=10-year,25-year,50-year,1pct_min,100-year,1pct_plu,500-year
River Rch & RM=WOLF HOLLOW CREE,Reach-1         ,14695
     155     327     534     287     868    2621    2447
River Rch & RM=WOLF HOLLOW CREE,Reach-1         ,12292
     240     525     876     479    1447    4369    4203
River Rch & RM=WOLF HOLLOW CREE,Reach-1         ,6944
     314     706    1190     657    1985    5994    5862
Boundary for River Rch & Prof#=WOLF HOLLOW CREE,Reach-1         , 1
Up Type= 0
Dn Type= 3
Dn Slope=0.0005
Boundary for River Rch & Prof#=WOLF HOLLOW CREE,Reach-1         , 2
Up Type= 0
Dn Type= 3
Dn Slope=0.0005
Boundary for River Rch & Prof#=WOLF HOLLOW CREE,Reach-1         , 3
Up Type= 0
Dn Type= 3
Dn Slope=0.0005
Boundary for River Rch & Prof#=WOLF HOLLOW CREE,Reach-1         , 4
Up Type= 0
Dn Type= 3
Dn Slope=0.0005
Boundary for River Rch & Prof#=WOLF HOLLOW CREE,Reach-1         , 5
Up Type= 0
Dn Type= 3
Dn Slope=0.0005
Boundary for River Rch & Prof#=WOLF HOLLOW CREE,Reach-1         , 6
Up Type= 0
Dn Type= 3
Dn Slope=0.0005
Boundary for River Rch & Prof#=WOLF HOLLOW CREE,Reach-1         , 7
Up Type= 0
Dn Type= 3
Dn Slope=0.0005
DSS Import GetInterval= 0
DSS Import GetPeak= 0
DSS Import FillOption= 0

--- WOLF HOLLOW CREEK.g01 (geometry) ---

Geom Title=Existing Conditions

River Reach=WOLF HOLLOW CREE,Reach-1
Reach XY= 30
      2835279.75     10185898.00      2835817.25     10186579.00
      2836251.75     10188819.00      2837122.75     10189496.00
      2837733.00     10189541.00      2838856.25     10191243.00
      2838654.25     10193382.00      2838793.25     10194076.00
      2839598.50     10194276.00      2839161.00     10195108.00
      2839349.50     10195319.00      2841799.50     10196258.00
      2842302.25     10195724.00      2843047.00     10195688.00
      2844410.25     10196144.00      2844873.75     10197080.00
      2846267.25     10196261.00      2847897.00     10196948.00
      2849601.25     10196236.00      2850259.50     10195508.00
      2851595.00     10196043.00      2851809.25     10194597.00
      2852888.75     10194391.00      2853233.50     10194870.00
      2852865.25     10194880.00      2852702.75     10196908.00
      2853179.00     10197637.00      2854136.00     10197707.00
      2854404.75     10198520.00      2854833.25     10198491.00

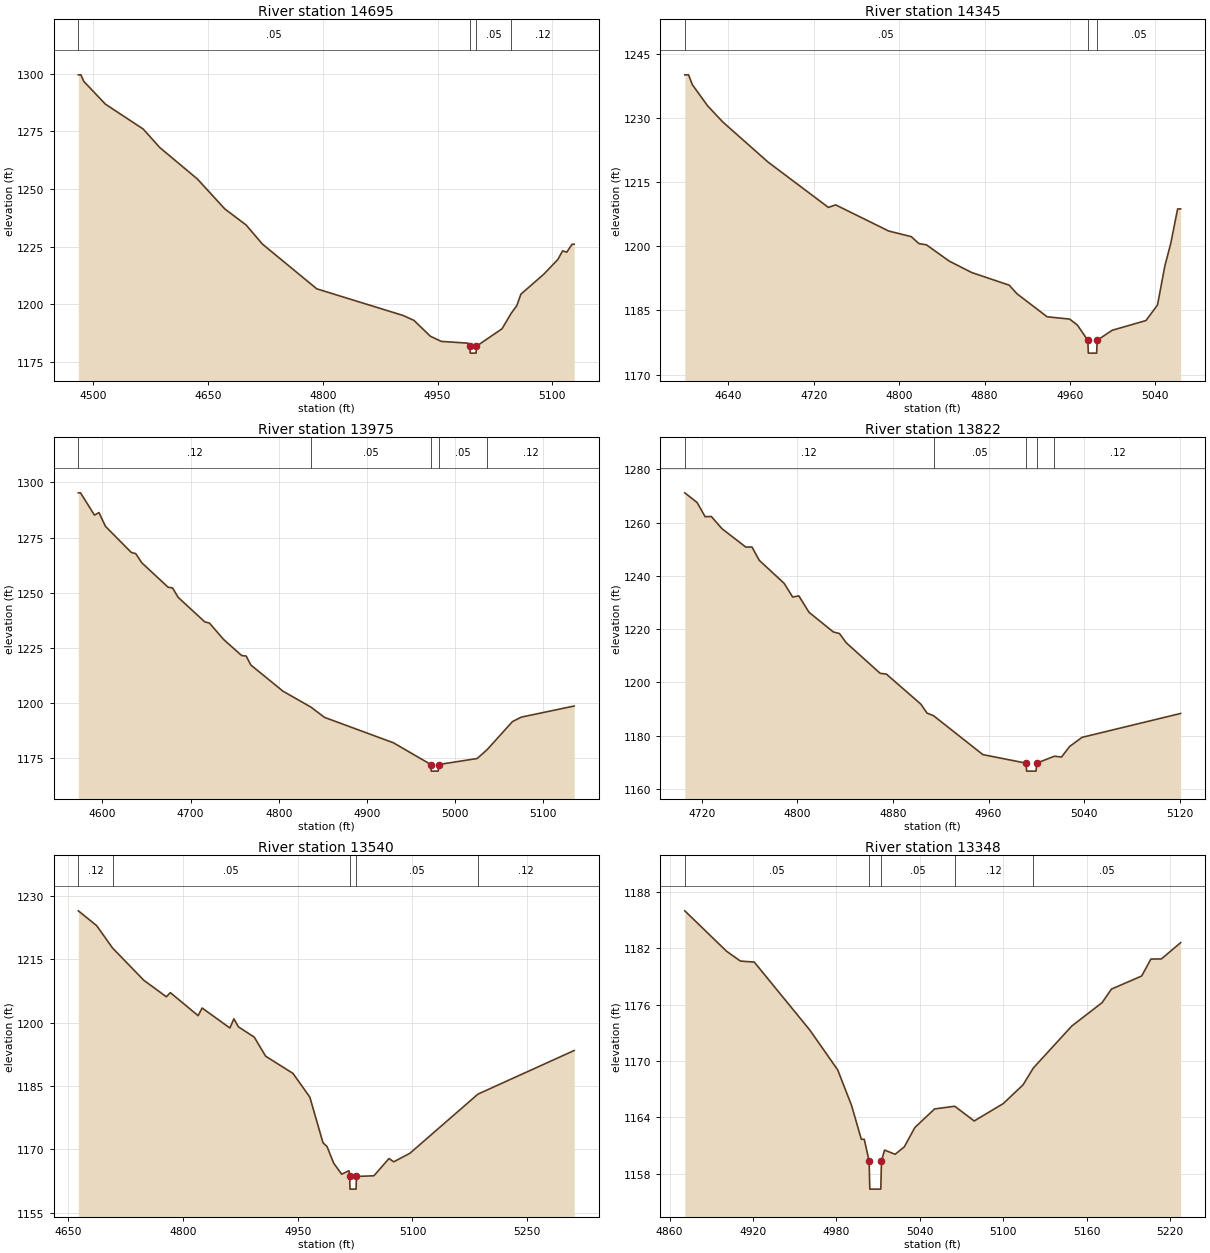
Type RM Length L Ch R = 1,14695,350,350,350
BEGIN DESCRIPTION:
WOLF HOLLOW CREEK 26.0
END DESCRIPTION:
XS GIS Cut Line= 3
      2846655.68     10196903.11      2847009.50     10196523.00
      2847055.69     10196403.09
#Sta/Elev= 30
  4480.7 1299.46  4484.1 1299.46  4487.8 1296.63  4516.1 1286.74  4565.5 1275.94
  4587.0 1267.96  4636.3 1254.27  4672.0 1241.33  4699.8 1234.38  4721.3 1226.04
  4792.2 1206.66  4905.0 1195.10  4919.2 1192.97  4940.7 1186.08  4954.9 1183.86
  4990.0 1183.09  4992.2 1181.77  4992.7 1178.77  5000.4 1178.77  5000.9 1181.77
  5034.3 1189.34  5046.2 1196.03  5053.5 1199.31  5058.9 1204.32  5088.9 1213.03
  5107.0 1219.31  5113.5 1223.13  5118.8 1222.53  5125.8 1225.99  5128.5 1225.99
#Mann=4,-1,0
  4480.7    0.05       0  4992.2    0.05       0  5000.9    0.05       0
  5046.2    0.12       0
Bank Sta=4992.2,5000.9
Exp/Cntr=0.3,0.1

Type RM Length L Ch R = 1,14345,370,370,370
BEGIN DESCRIPTION:
WOLF HOLLOW CREEK 25.0
END DESCRIPTION:
XS GIS Cut Line= 3
      2847055.65     10196953.15      2847331.25     10196662.00
      2847355.70     10196603.07
#Sta/Elev= 30
  4599.1 1240.12  4602.6 1240.12  4606.2 1237.81  4620.4 1232.90  4634.5 1229.14
  4677.0 1219.74  4733.7 1209.11  4740.5 1209.70  4790.3 1203.58  4811.3 1202.28
  4818.6 1200.64  4825.5 1200.37  4846.9 1196.56  4868.0 1193.88  4903.2 1190.92
  4910.4 1188.92  4938.7 1183.53  4959.8 1182.99  4967.1 1181.58  4976.8 1178.03
  4977.3 1175.03  4985.1 1175.03  4985.6 1178.03  4999.6 1180.37  5031.3 1182.65
  5042.1 1186.27  5049.1 1195.51  5054.5 1200.64  5061.0 1208.76  5063.8 1208.76
#Mann=3,-1,0
  4599.1    0.05       0  4976.8    0.03       0  4985.6    0.05       0
Bank Sta=4976.8,4985.6
Exp/Cntr=0.3,0.1

Type RM Length L Ch R = 1,13975,153,153,153
BEGIN DESCRIPTION:
WOLF HOLLOW CREEK 24.0
END DESCRIPTION:
XS GIS Cut Line= 3
      2847555.69     10197253.08      2847656.75     10196838.00
      2847655.68     10196703.10
#Sta/Elev= 30
  4572.8 1295.26  4575.3 1295.26  4591.1 1285.17  4596.2 1286.31  4603.6 1280.06
  4632.8 1268.28  4637.9 1267.70  4644.8 1263.56  4674.5 1252.52  4679.6 1252.18
  4686.0 1247.90  4716.2 1236.79  4721.4 1236.29  4737.4 1228.89  4757.9 1221.57
  4763.1 1221.33  4768.3 1217.29  4804.8 1205.42  4836.7 1198.15  4851.7 1193.58
  4930.0 1182.04  4972.4 1172.20  4972.9 1169.20  4980.8 1169.20  4981.3 1172.20
  5024.9 1174.90  5036.3 1178.95  5064.9 1191.62  5074.9 1193.65  5134.9 1198.69
#Mann=5,-1,0
  4572.8    0.12       0  4836.7    0.05       0  4972.4    0.05       0
  4981.3    0.05       0  5036.3    0.12       0
Bank Sta=4972.4,4981.3
Exp/Cntr=0.3,0.1

Type RM Length L Ch R = 1,13822,282,282,282
BEGIN DESCRIPTION:
WOLF HOLLOW CREEK 23.0
END DESCRIPTION:
XS GIS Cut Line= 3
      2847705.70     10197203.07      2847785.50     10196920.00
      2847755.69     10196803.14
#Sta/Elev= 30
  4705.9 1271.17  4716.2 1267.54  4722.9 1262.21  4728.1 1262.29  4737.0 1257.70
  4756.9 1250.82  4762.1 1250.82  4768.2 1245.83  4789.0 1237.20  4796.1 1232.06
  4801.3 1232.48  4809.8 1226.33  4830.1 1218.96  4835.3 1218.34  4840.9 1214.90
  4869.3 1203.42  4874.5 1203.13  4903.3 1191.87  4908.5 1188.50  4914.0 1187.50
  4955.2 1172.91  4991.3 1169.71  4991.8 1166.71  4999.7 1166.71  5000.2 1169.71
  5015.1 1172.31  5021.0 1172.00  5027.7 1175.94  5038.1 1179.38  5120.6 1188.36
#Mann=5,-1,0
  4705.9    0.12       0  4914.0    0.05       0  4991.3    0.05       0
  5000.2    0.05       0  5015.1    0.12       0
Bank Sta=4991.3,5000.2
Exp/Cntr=0.3,0.1

Type RM Length L Ch R = 1,13540,192,192,192
BEGIN DESCRIPTION:
Mapping XS 8d37d6e3
END DESCRIPTION:
XS GIS Cut Line= 4
      2848012.30     10197206.27      2848071.13     10196967.51
      2848033.07     10196832.58      2847825.46     10196673.41
#Sta/Elev= 30
  4663.5 1226.50  4687.4 1223.00  4708.2 1217.70  4749.1 1210.05  4778.5 1206.15
  4783.7 1207.13  4820.0 1201.68  4825.2 1203.49  4861.5 1198.76  4866.7 1200.93
  4872.7 1199.02  4893.3 1196.60  4908.2 1192.08  4943.9 1188.01  4965.9 1182.40
  4983.1 1171.59  4988.3 1170.72  4997.1 1166.75  5007.5 1164.14  5017.1 1164.97
  5017.9 1163.61  5018.4 1160.61  5026.3 1160.61  5026.8 1163.61  5049.6 1163.77
  5069.3 1167.85  5075.6 1167.08  5096.7 1169.11  5185.5 1183.10  5311.2 1193.43
#Mann=5,-1,0
  4663.5    0.12       0  4708.2    0.05       0  5017.9    0.05       0
  5026.8    0.05       0  5185.5    0.12       0
Bank Sta=5017.9,5026.8
Exp/Cntr=0.3,0.1

Type RM Length L Ch R = 1,13348,350,350,350
BEGIN DESCRIPTION:
WOLF HOLLOW CREEK 22.0
END DESCRIPTION:
XS GIS Cut Line= 3
      2848205.68     10196903.10      2848206.00     10196774.00
      2848055.68     10196603.10
#Sta/Elev= 30
  4870.9 1185.98  4900.9 1181.68  4910.9 1180.63  4920.9 1180.52  4960.9 1173.27
  4980.9 1169.04  4990.9 1165.24  4997.9 1161.65  5000.0 1161.65  5003.5 1159.34
  5004.0 1156.34  5011.9 1156.34  5012.4 1159.34  5014.6 1160.50  5022.2 1160.05
  5028.8 1160.84  5036.4 1162.90  5050.6 1164.88  5065.1 1165.17  5079.1 1163.60
  5100.0 1165.45  5114.2 1167.44  5121.7 1169.25  5149.3 1173.71  5171.1 1176.20
  5177.8 1177.64  5199.6 1179.04  5206.2 1180.84  5213.8 1180.86  5227.6 1182.59
#Mann=5,-1,0
  4870.9    0.05       0  5003.5    0.05       0  5012.4    0.05       0
  5065.1    0.12       0  5121.7    0.05       0
Bank Sta=5003.5,5012.4
Exp/Cntr=0.3,0.1

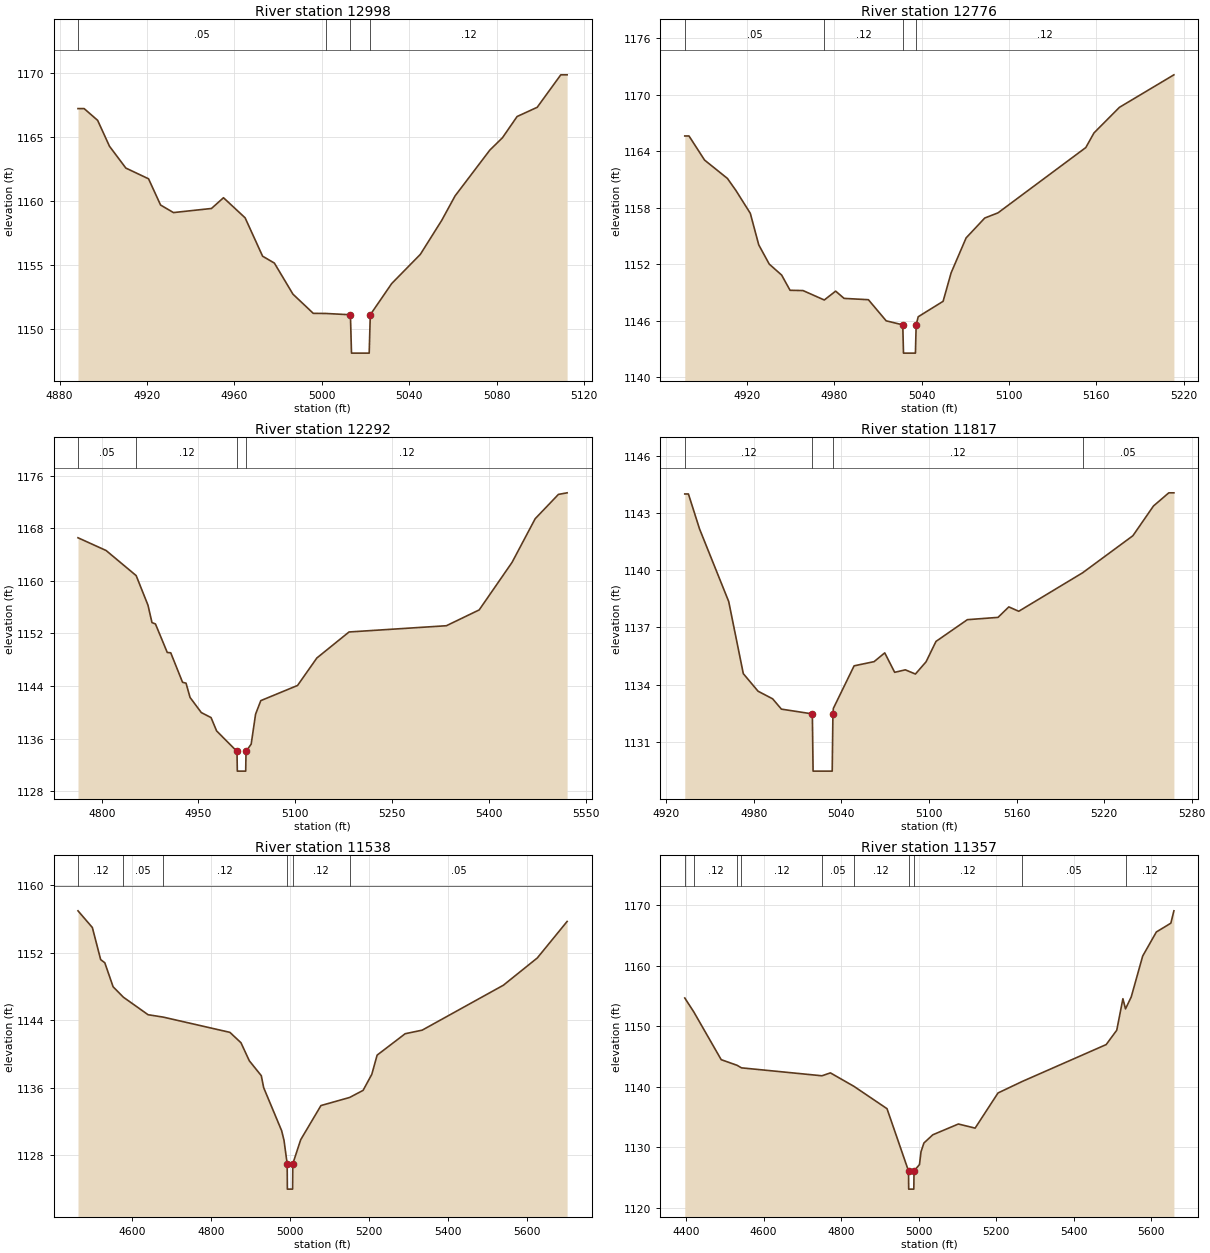
Type RM Length L Ch R = 1,12998,222,222,222
BEGIN DESCRIPTION:
WOLF HOLLOW CREEK 21.0
END DESCRIPTION:
XS GIS Cut Line= 3
      2848555.70     10196703.15      2848510.75     10196601.00
      2848455.69     10196503.12
#Sta/Elev= 30
  4888.4 1167.25  4891.2 1167.25  4897.4 1166.33  4902.8 1164.31  4910.3 1162.60
  4920.7 1161.76  4926.2 1159.71  4932.1 1159.12  4949.5 1159.44  4955.0 1160.28
  4964.9 1158.71  4972.9 1155.71  4978.3 1155.17  4986.8 1152.74  4996.1 1151.24
  5001.9 1151.23  5013.1 1151.13  5013.6 1148.13  5021.7 1148.13  5022.2 1151.13
  5032.0 1153.57  5045.1 1155.85  5054.9 1158.51  5061.0 1160.42  5076.9 1164.00
  5082.7 1164.97  5089.4 1166.63  5098.6 1167.35  5109.4 1169.89  5112.3 1169.89
#Mann=4,-1,0
  4888.4    0.05       0  5001.9    0.12       0  5013.1    0.03       0
  5022.2    0.12       0
Bank Sta=5013.1,5022.2
Exp/Cntr=0.3,0.1

Type RM Length L Ch R = 1,12776,484,484,484
BEGIN DESCRIPTION:
WOLF HOLLOW CREEK 20.0
END DESCRIPTION:
XS GIS Cut Line= 3
      2848805.70     10196553.12      2848700.00     10196491.00
      2848505.65     10196403.10
#Sta/Elev= 30
  4877.4 1165.62  4880.3 1165.62  4891.0 1163.06  4906.7 1161.11  4912.5 1159.84
  4922.4 1157.41  4928.2 1154.06  4935.4 1152.02  4943.9 1150.86  4949.7 1149.24
  4958.6 1149.21  4973.2 1148.21  4981.0 1149.15  4986.8 1148.38  5003.5 1148.24
  5015.7 1146.00  5027.1 1145.57  5027.6 1142.57  5035.8 1142.57  5036.3 1145.57
  5037.7 1146.43  5054.8 1148.07  5060.3 1151.09  5070.6 1154.80  5083.4 1156.91
  5092.5 1157.46  5152.8 1164.39  5158.4 1165.94  5175.9 1168.66  5213.3 1172.11
#Mann=4,-1,0
  4877.4    0.05       0  4973.2    0.12       0  5027.1    0.07       0
  5036.3    0.12       0
Bank Sta=5027.1,5036.3
Exp/Cntr=0.3,0.1

Type RM Length L Ch R = 1,12292,475,475,475
BEGIN DESCRIPTION:
WOLF HOLLOW CREEK 19.0
END DESCRIPTION:
XS GIS Cut Line= 3
      2849055.70     10196553.07      2849148.00     10196335.00
      2848855.69     10195903.12
#Sta/Elev= 30
  4763.2 1166.56  4806.8 1164.62  4853.4 1160.80  4871.7 1156.30  4877.9 1153.65
  4883.3 1153.44  4901.6 1149.10  4907.0 1149.05  4925.3 1144.56  4930.7 1144.43
  4936.9 1142.26  4954.4 1139.95  4969.5 1139.19  4978.1 1137.16  5009.7 1134.04
  5010.2 1131.04  5023.2 1131.04  5023.7 1134.04  5031.7 1135.15  5038.5 1139.70
  5046.6 1141.77  5103.6 1144.08  5133.5 1148.26  5183.4 1152.22  5334.3 1153.17
  5385.2 1155.58  5436.1 1162.81  5472.0 1169.46  5508.0 1173.16  5521.5 1173.40
#Mann=4,-1,0
  4763.2    0.05       0  4853.4    0.12       0  5009.7    0.07       0
  5023.7    0.12       0
Bank Sta=5009.7,5023.7
Exp/Cntr=0.3,0.1

Type RM Length L Ch R = 1,11817,279,279,279
BEGIN DESCRIPTION:
WOLF HOLLOW CREEK 18.0
END DESCRIPTION:
XS GIS Cut Line= 3
      2849605.69     10196303.15      2849601.25     10196236.00
      2849405.65     10196053.08
#Sta/Elev= 30
  4932.7 1143.99  4935.2 1143.99  4942.8 1142.16  4962.8 1138.35  4972.8 1134.57
  4982.9 1133.65  4992.9 1133.25  4998.9 1132.71  5020.1 1132.46  5020.6 1129.46
  5033.7 1129.46  5034.2 1132.46  5034.5 1132.75  5048.7 1134.98  5062.4 1135.20
  5069.7 1135.66  5076.5 1134.64  5083.8 1134.77  5090.7 1134.55  5098.0 1135.19
  5104.8 1136.26  5126.3 1137.40  5147.3 1137.52  5154.7 1138.07  5161.5 1137.84
  5205.3 1139.86  5239.7 1141.80  5253.8 1143.36  5264.3 1144.05  5267.8 1144.05
#Mann=4,-1,0
  4932.7    0.12       0  5020.1    0.07       0  5034.2    0.12       0
  5205.3    0.05       0
Bank Sta=5020.1,5034.2
Exp/Cntr=0.3,0.1

Type RM Length L Ch R = 1,11538,181,181,181
BEGIN DESCRIPTION:
Mapping XS 2abba18e
END DESCRIPTION:
XS GIS Cut Line= 4
      2849984.46     10196517.68      2849870.29     10196161.35
      2849749.20     10195974.51      2849334.61     10195487.37
#Sta/Elev= 30
  4463.9 1156.96  4500.2 1154.98  4521.2 1151.18  4531.7 1150.80  4552.7 1147.95
  4578.6 1146.72  4641.1 1144.64  4679.1 1144.36  4847.9 1142.55  4875.9 1141.32
  4897.0 1139.18  4927.3 1137.41  4933.3 1135.99  4978.7 1130.89  4984.7 1129.75
  4992.7 1126.96  4993.2 1123.96  5006.4 1123.96  5006.9 1126.96  5026.9 1129.82
  5078.1 1133.87  5150.6 1134.83  5184.6 1135.67  5206.6 1137.57  5220.1 1139.85
  5291.1 1142.39  5334.0 1142.81  5539.3 1148.14  5625.0 1151.37  5700.4 1155.70
#Mann=6,-1,0
  4463.9    0.12       0  4578.6    0.05       0  4679.1    0.12       0
  4992.7    0.07       0  5006.9    0.12       0  5150.6    0.05       0
Bank Sta=4992.7,5006.9
Exp/Cntr=0.3,0.1

Type RM Length L Ch R = 1,11357,373,373,373
BEGIN DESCRIPTION:
WOLF HOLLOW CREEK 17.0
END DESCRIPTION:
XS GIS Cut Line= 3
      2850055.70     10196453.16      2849883.00     10195875.00
      2849555.70     10195303.14
#Sta/Elev= 30
  4396.6 1154.65  4419.9 1152.35  4490.6 1144.47  4531.6 1143.54  4542.9 1143.12
  4750.7 1141.81  4772.4 1142.29  4833.1 1140.07  4918.5 1136.38  4974.0 1126.10
  4974.5 1123.10  4987.7 1123.10  4988.2 1126.10  5002.3 1127.16  5006.3 1129.29
  5013.7 1130.71  5036.7 1132.07  5102.7 1133.85  5145.9 1133.17  5204.9 1138.97
  5267.4 1140.87  5484.1 1146.96  5511.4 1149.33  5527.3 1154.53  5534.0 1152.85
  5548.8 1154.83  5578.3 1161.57  5613.6 1165.55  5651.0 1167.00  5658.9 1169.04
#Mann=10,-1,0
  4396.6    0.05       0  4419.9    0.12       0  4531.6    0.05       0
  4542.9    0.12       0  4750.7    0.05       0  4833.1    0.12       0
  4974.0    0.07       0  4988.2    0.12       0  5267.4    0.05       0
  5534.0    0.12       0
Bank Sta=4974,4988.2
Exp/Cntr=0.3,0.1

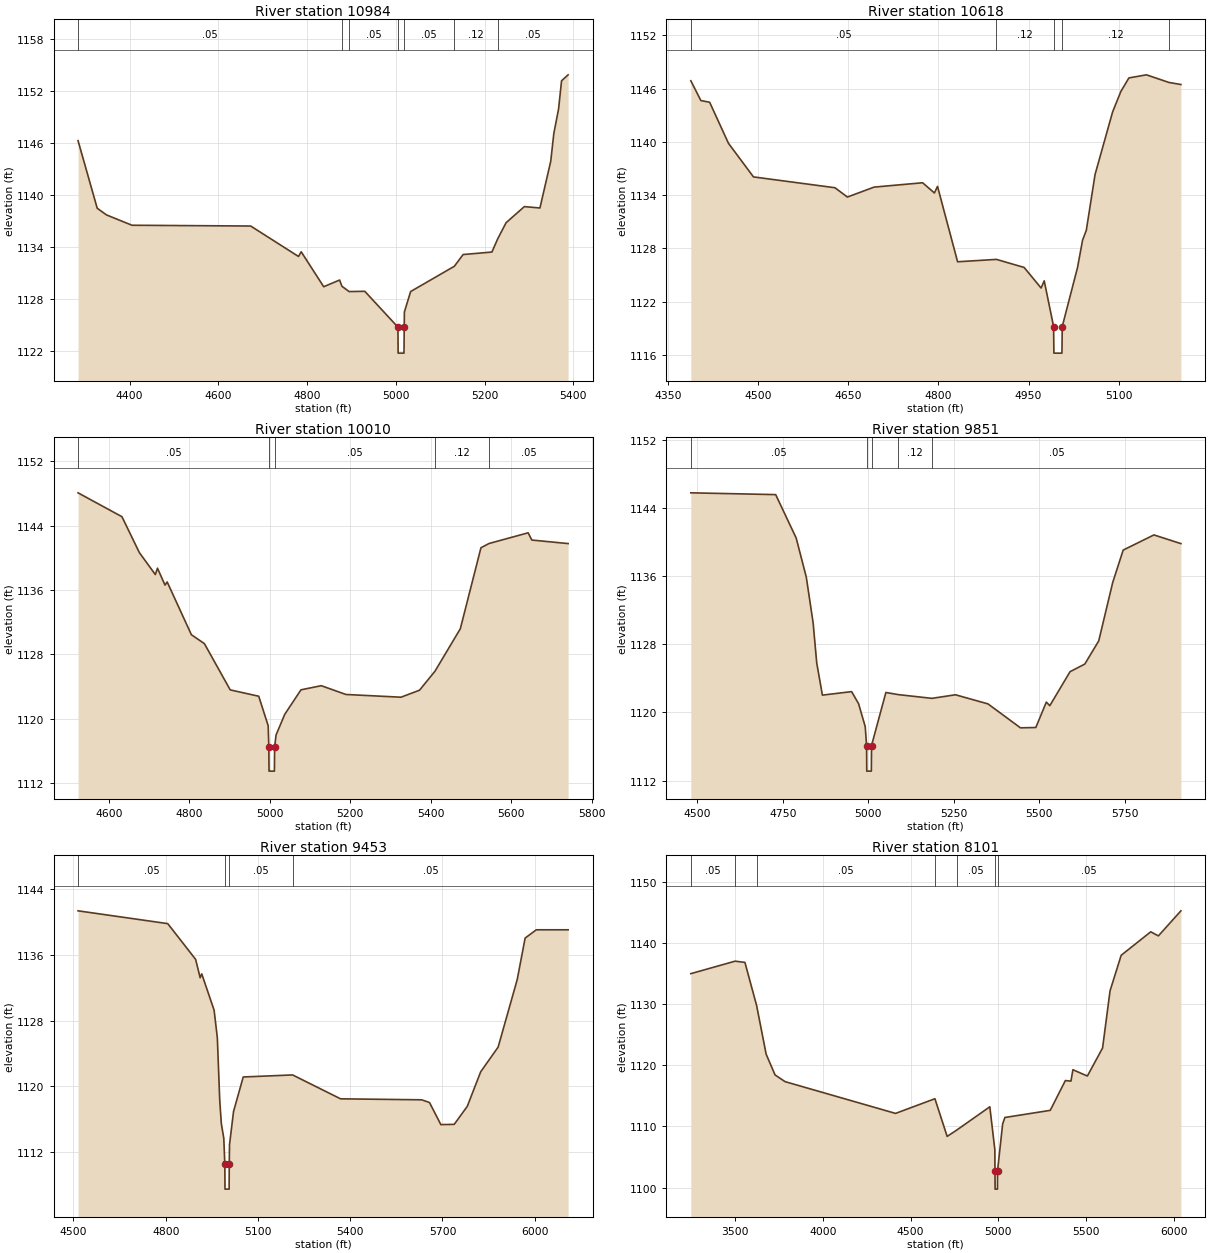
Type RM Length L Ch R = 1,10984,366,366,366
BEGIN DESCRIPTION:
WOLF HOLLOW CREEK 16.0
END DESCRIPTION:
XS GIS Cut Line= 3
      2850555.66     10196203.08      2850148.50     10195614.00
      2850005.69     10195253.13
#Sta/Elev= 30
  4283.9 1146.22  4327.1 1138.42  4348.1 1137.65  4405.4 1136.46  4672.9 1136.37
  4780.6 1132.86  4786.7 1133.40  4837.4 1129.37  4873.2 1130.14  4878.5 1129.42
  4894.7 1128.81  4930.0 1128.84  5004.6 1124.71  5005.1 1121.71  5018.3 1121.71
  5018.8 1124.71  5019.2 1126.45  5033.2 1128.81  5131.8 1131.73  5151.5 1133.08
  5216.4 1133.37  5229.6 1134.91  5248.3 1136.75  5289.5 1138.61  5324.6 1138.45
  5348.9 1143.83  5355.9 1147.04  5366.6 1149.88  5373.3 1153.12  5388.1 1153.81
#Mann=7,-1,0
  4283.9    0.05       0  4878.5    0.12       0  4894.7    0.05       0
  5004.6    0.05       0  5018.8    0.05       0  5131.8    0.12       0
  5229.6    0.05       0
Bank Sta=5004.6,5018.8
Exp/Cntr=0.3,0.1

Type RM Length L Ch R = 1,10618,608,608,608
BEGIN DESCRIPTION:
WOLF HOLLOW CREEK 15.0
END DESCRIPTION:
XS GIS Cut Line= 3
      2850605.69     10196203.14      2850433.75     10195616.00
      2850555.70     10195453.09
#Sta/Elev= 30
  4388.2 1146.89  4404.9 1144.66  4419.5 1144.47  4450.8 1139.84  4492.4 1136.05
  4627.9 1134.83  4648.7 1133.78  4693.1 1134.90  4773.8 1135.39  4793.4 1134.24
  4798.6 1134.98  4832.0 1126.48  4896.6 1126.75  4942.7 1125.84  4970.9 1123.52
  4976.1 1124.33  4991.7 1119.18  4992.2 1116.18  5005.6 1116.18  5006.1 1119.18
  5031.5 1125.83  5039.9 1128.92  5046.1 1130.02  5060.7 1136.33  5089.9 1143.38
  5103.5 1145.67  5117.0 1147.21  5146.2 1147.56  5183.6 1146.70  5203.5 1146.47
#Mann=5,-1,0
  4388.2    0.05       0  4896.6    0.12       0  4991.7    0.07       0
  5006.1    0.12       0  5183.6    0.05       0
Bank Sta=4991.7,5006.1
Exp/Cntr=0.3,0.1

Type RM Length L Ch R = 1,10010,159,159,159
BEGIN DESCRIPTION:
Mapping XS 0da78d14
END DESCRIPTION:
XS GIS Cut Line= 5
      2850797.57     10196334.31      2850932.49     10196002.19
      2850974.01     10195870.71      2850953.25     10195718.48
      2850773.35     10195178.77
#Sta/Elev= 30
  4522.9 1148.08  4632.1 1145.11  4675.3 1140.66  4715.1 1137.92  4720.5 1138.71
  4739.2 1136.61  4744.6 1137.00  4804.8 1130.44  4837.2 1129.33  4901.4 1123.58
  4972.3 1122.79  4995.8 1119.13  4997.4 1116.48  4997.9 1113.48  5011.3 1113.48
  5011.8 1116.48  5015.4 1117.97  5037.0 1120.54  5077.4 1123.59  5127.9 1124.10
  5189.1 1123.01  5326.1 1122.67  5372.2 1123.54  5410.6 1125.90  5473.7 1131.18
  5525.0 1141.25  5545.1 1141.78  5642.4 1143.11  5651.5 1142.21  5741.8 1141.77
#Mann=5,-1,0
  4522.9    0.05       0  4997.4    0.05       0  5011.8    0.05       0
  5410.6    0.12       0  5545.1    0.05       0
Bank Sta=4997.4,5011.8
Exp/Cntr=0.3,0.1

Type RM Length L Ch R = 1,9851,398,398,398
BEGIN DESCRIPTION:
Mapping XS a83b9bbf
END DESCRIPTION:
XS GIS Cut Line= 5
      2851019.00     10196465.80      2851084.73     10196085.23
      2851122.79     10195901.85      2851143.55     10195721.94
      2851005.21     10195057.89
#Sta/Elev= 30
  4480.8 1145.77  4728.9 1145.56  4788.8 1140.47  4818.4 1135.88  4838.4 1130.50
  4848.9 1125.81  4865.5 1122.03  4950.9 1122.44  4971.3 1121.02  4990.7 1118.33
  4994.7 1116.11  4995.2 1113.11  5008.6 1113.11  5009.1 1116.11  5051.1 1122.34
  5087.1 1122.09  5185.6 1121.65  5254.6 1122.07  5349.6 1121.00  5444.6 1118.19
  5489.5 1118.23  5520.2 1121.21  5530.4 1120.79  5589.6 1124.78  5632.6 1125.67
  5673.4 1128.39  5714.3 1135.25  5744.9 1139.05  5834.8 1140.83  5913.7 1139.81
#Mann=5,-1,0
  4480.8    0.05       0  4994.7    0.03       0  5009.1    0.05       0
  5087.1    0.12       0  5185.6    0.05       0
Bank Sta=4994.7,5009.1
Exp/Cntr=0.3,0.1

Type RM Length L Ch R = 1,9453,1352,1352,1352
BEGIN DESCRIPTION:
Mapping XS 56404887
END DESCRIPTION:
XS GIS Cut Line= 5
      2851299.23     10196507.38      2851496.46     10196182.11
      2851434.19     10195991.81      2851254.27     10195458.98
      2851105.50     10195033.45
#Sta/Elev= 30
  4514.9 1141.37  4806.7 1139.81  4897.4 1135.45  4912.0 1133.22  4917.2 1133.69
  4957.4 1129.27  4967.9 1125.92  4975.7 1118.30  4980.9 1115.45  4988.9 1113.67
  4992.3 1110.47  4992.8 1107.47  5006.2 1107.47  5006.7 1110.47  5007.5 1112.88
  5020.5 1116.91  5052.1 1121.13  5212.7 1121.38  5368.6 1118.47  5632.4 1118.35
  5657.9 1118.02  5694.8 1115.33  5738.3 1115.36  5780.7 1117.55  5824.3 1121.76
  5881.1 1124.77  5943.2 1133.00  5968.9 1138.05  6005.3 1139.06  6108.7 1139.06
#Mann=4,-1,0
  4514.9    0.05       0  4992.3    0.07       0  5006.7    0.05       0
  5212.7    0.05       0
Bank Sta=4992.3,5006.7
Exp/Cntr=0.3,0.1

Type RM Length L Ch R = 1,8101,1157,1157,1157
BEGIN DESCRIPTION:
Mapping XS 3c7c86da
END DESCRIPTION:
XS GIS Cut Line= 5
      2851579.53     10196462.32      2852012.00     10195801.51
      2851859.76     10195092.23      2851472.24     10194818.89
      2850714.51     10194552.47
#Sta/Elev= 30
  3247.7 1134.99  3500.1 1137.03  3555.9 1136.83  3622.5 1129.79  3677.0 1121.81
  3727.7 1118.43  3785.0 1117.33  4414.2 1112.14  4638.6 1114.54  4708.3 1108.38
  4761.7 1109.39  4951.4 1113.22  4980.1 1106.21  4980.9 1102.76  4981.4 1099.76
  4994.9 1099.76  4995.4 1102.76  5024.5 1110.41  5037.1 1111.47  5295.7 1112.64
  5381.9 1117.51  5413.7 1117.42  5424.9 1119.28  5507.3 1118.25  5593.9 1122.83
  5636.5 1132.18  5699.9 1137.99  5868.4 1141.83  5911.9 1141.16  6040.3 1145.26
#Mann=7,-1,0
  3247.7    0.05       0  3500.1    0.12       0  3622.5    0.05       0
  4638.6    0.12       0  4761.7    0.05       0  4980.9    0.03       0
  4995.4    0.05       0
Bank Sta=4980.9,4995.4
Exp/Cntr=0.3,0.1

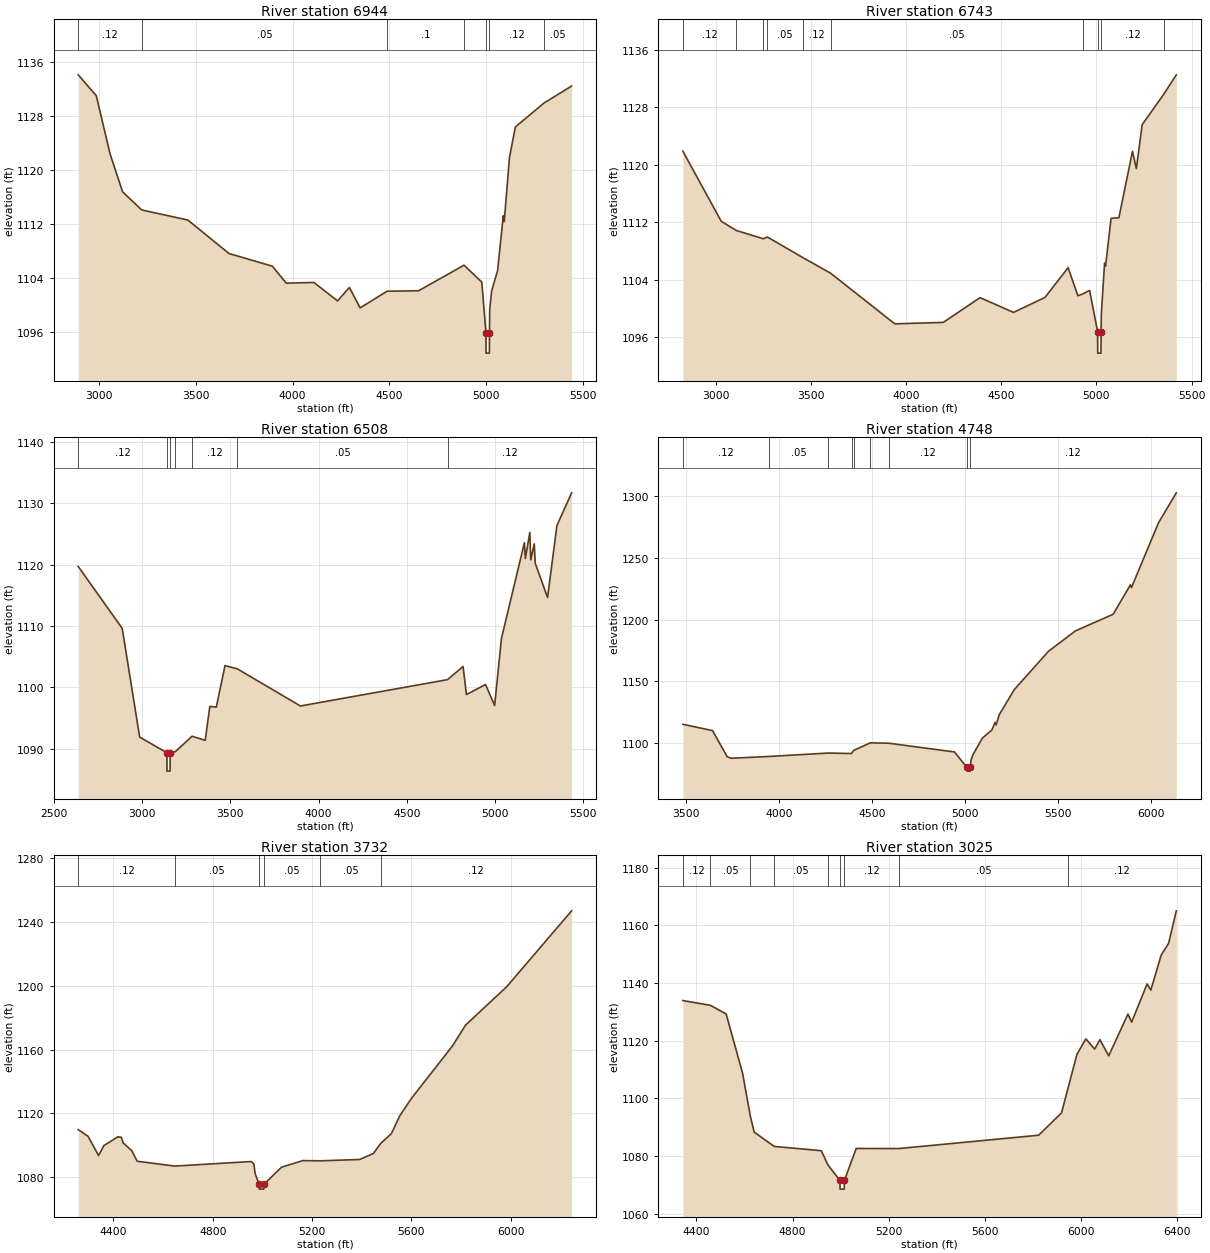
Type RM Length L Ch R = 1,6944,201,201,201
BEGIN DESCRIPTION:
Mapping XS 82dc2713
END DESCRIPTION:
XS GIS Cut Line= 4
      2851814.80     10196372.38      2852274.95     10195739.24
      2852593.26     10194192.64      2852551.75     10194009.29
#Sta/Elev= 30
  2892.4 1134.04  2985.8 1130.95  3056.9 1122.33  3121.9 1116.70  3220.7 1114.02
  3458.8 1112.53  3671.5 1107.57  3895.7 1105.69  3967.2 1103.18  4110.1 1103.28
  4232.7 1100.55  4293.8 1102.54  4349.2 1099.51  4488.4 1101.98  4651.3 1102.05
  4886.3 1105.84  4978.0 1103.32  4999.5 1095.81  5000.0 1092.81  5017.2 1092.81
  5017.7 1095.81  5018.8 1099.31  5029.0 1102.06  5059.6 1105.03  5088.8 1113.16
  5093.9 1112.30  5120.9 1121.80  5151.5 1126.32  5299.3 1129.86  5442.1 1132.38
#Mann=7,-1,0
  2892.4    0.12       0  3220.7    0.05       0  4488.4     0.1       0
  4886.3    0.12       0  4999.5    0.07       0  5017.7    0.12       0
  5299.3    0.05       0
Bank Sta=4999.5,5017.7
Exp/Cntr=0.3,0.1

Type RM Length L Ch R = 1,6743,235,235,235
BEGIN DESCRIPTION:
Mapping XS 7e66134b
END DESCRIPTION:
XS GIS Cut Line= 5
      2851988.76     10196415.59      2852461.83     10195712.50
      2852670.16     10194731.59      2852769.99     10194288.89
      2852713.69     10194007.40
#Sta/Elev= 30
  2828.5 1121.91  3029.7 1112.15  3109.5 1110.86  3251.4 1109.71  3272.1 1109.96
  3460.2 1107.06  3604.0 1104.92  3941.1 1097.86  4195.7 1098.06  4389.1 1101.51
  4564.7 1099.45  4730.0 1101.54  4851.4 1105.69  4902.7 1101.78  4927.5 1102.01
  4964.2 1102.52  5006.3 1096.78  5006.8 1093.78  5024.0 1093.78  5024.5 1096.78
  5025.7 1099.22  5042.9 1106.32  5048.1 1105.90  5076.9 1112.56  5118.0 1112.64
  5189.4 1121.89  5209.8 1119.48  5240.4 1125.61  5353.6 1129.85  5419.6 1132.55
#Mann=10,-1,0
  2828.5    0.12       0  3109.5    0.05       0  3251.4    0.12       0
  3272.1    0.05       0  3460.2    0.12       0  3604.0    0.05       0
  4927.5    0.12       0  5006.3    0.07       0  5024.5    0.12       0
  5353.6    0.05       0
Bank Sta=5006.3,5024.5
Exp/Cntr=0.3,0.1

Type RM Length L Ch R = 1,6508,1760,1760,1760
BEGIN DESCRIPTION:
Mapping XS 879528e9
END DESCRIPTION:
XS GIS Cut Line= 6
      2852036.51     10196515.41      2852396.72     10196098.78
      2852765.65     10194822.74      2852960.96     10194571.00
      2852978.32     10194293.23      2852870.24     10193994.92
#Sta/Elev= 30
  2638.8 1119.71  2888.1 1109.62  2986.9 1091.91  3141.1 1089.37  3141.6 1086.37
  3159.0 1086.37  3159.5 1089.37  3189.1 1089.54  3283.5 1092.05  3358.2 1091.39
  3384.3 1096.92  3420.9 1096.79  3470.2 1103.56  3539.4 1103.04  3897.4 1096.98
  4730.5 1101.27  4818.7 1103.41  4837.7 1098.84  4946.0 1100.48  4997.4 1097.06
  5036.2 1108.01  5166.1 1123.58  5171.4 1120.99  5196.7 1125.25  5202.0 1120.79
  5222.0 1123.39  5227.4 1120.23  5297.2 1114.65  5350.3 1126.37  5433.5 1131.70
#Mann=7,-1,0
  2638.8    0.12       0  3141.1    0.07       0  3159.5    0.12       0
  3189.1    0.05       0  3283.5    0.12       0  3539.4    0.05       0
  4730.5    0.12       0
Bank Sta=3141.1,3159.5
Exp/Cntr=0.3,0.1

Type RM Length L Ch R = 1,4748,1016,1016,1016
BEGIN DESCRIPTION:
Mapping XS acfb438e
END DESCRIPTION:
XS GIS Cut Line= 5
      2852145.00     10196610.91      2852579.02     10195920.83
      2852683.18     10195538.89      2853247.42     10195269.79
      2853989.59     10194939.94
#Sta/Elev= 30
  3485.8 1115.11  3644.7 1110.01  3723.6 1088.80  3744.8 1087.56  3948.3 1089.02
  4266.1 1091.79  4390.9 1091.40  4402.8 1093.94  4491.6 1100.07  4592.3 1099.74
  4943.4 1092.68  5010.4 1080.13  5010.9 1077.13  5028.4 1077.13  5028.9 1080.13
  5032.1 1085.92  5042.4 1090.40  5093.3 1103.90  5144.2 1110.49  5161.4 1116.62
  5166.9 1114.62  5184.1 1122.98  5264.7 1143.26  5447.6 1174.23  5592.6 1190.84
  5795.1 1204.32  5888.1 1228.21  5893.6 1225.98  6038.6 1278.51  6134.2 1302.80
#Mann=9,-1,0
  3485.8    0.12       0  3948.3    0.05       0  4266.1    0.12       0
  4390.9    0.05       0  4402.8    0.12       0  4491.6    0.05       0
  4592.3    0.12       0  5010.4    0.07       0  5028.9    0.12       0
Bank Sta=5010.4,5028.9
Exp/Cntr=0.3,0.1

Type RM Length L Ch R = 1,3732,707,707,707
BEGIN DESCRIPTION:
Mapping XS ab30e69f
END DESCRIPTION:
XS GIS Cut Line= 3
      2852105.95     10196819.25      2852479.19     10196437.32
      2853876.56     10196038.08
#Sta/Elev= 30
  4258.1 1109.81  4297.6 1105.61  4340.0 1093.52  4361.3 1099.74  4417.9 1105.28
  4432.0 1104.92  4439.0 1101.49  4474.5 1096.43  4495.6 1089.95  4646.4 1086.91
  4954.9 1089.77  4965.3 1088.38  4970.9 1082.06  4987.2 1075.46  4987.7 1072.46
  5005.2 1072.46  5005.7 1075.46  5077.5 1086.26  5162.9 1090.35  5233.1 1090.21
  5391.7 1091.04  5446.7 1094.77  5475.9 1101.01  5519.5 1107.30  5553.3 1118.48
  5599.7 1129.25  5766.1 1162.39  5818.1 1175.31  5984.5 1199.49  6245.4 1247.00
#Mann=6,-1,0
  4258.1    0.12       0  4646.4    0.05       0  4987.2    0.03       0
  5005.7    0.05       0  5233.1    0.05       0  5475.9    0.12       0
Bank Sta=4987.2,5005.7
Exp/Cntr=0.3,0.1

Type RM Length L Ch R = 1,3025,468,468,468
BEGIN DESCRIPTION:
Mapping XS c1a9d883
END DESCRIPTION:
XS GIS Cut Line= 2
      2852231.83     10197387.82      2853992.30     10196334.14
#Sta/Elev= 30
  4344.1 1133.91  4458.6 1132.26  4524.0 1129.24  4592.1 1108.77  4624.9 1093.67
  4640.7 1088.24  4724.0 1083.30  4919.7 1081.82  4947.1 1076.90  4997.0 1071.49
  4997.5 1068.49  5015.2 1068.49  5015.7 1071.49  5064.7 1082.60  5240.9 1082.56
  5823.1 1087.19  5918.4 1094.92  5946.3 1103.78  5982.6 1115.25  6019.5 1120.61
  6056.5 1117.07  6077.9 1120.35  6114.8 1114.75  6194.6 1129.22  6210.1 1126.44
  6274.3 1139.66  6289.9 1137.55  6332.7 1149.64  6363.8 1153.78  6395.8 1165.04
#Mann=9,-1,0
  4344.1    0.12       0  4458.6    0.05       0  4624.9    0.12       0
  4724.0    0.05       0  4947.1    0.12       0  4997.0    0.07       0
  5015.7    0.12       0  5240.9    0.05       0  5946.3    0.12       0
Bank Sta=4997,5015.7
Exp/Cntr=0.3,0.1

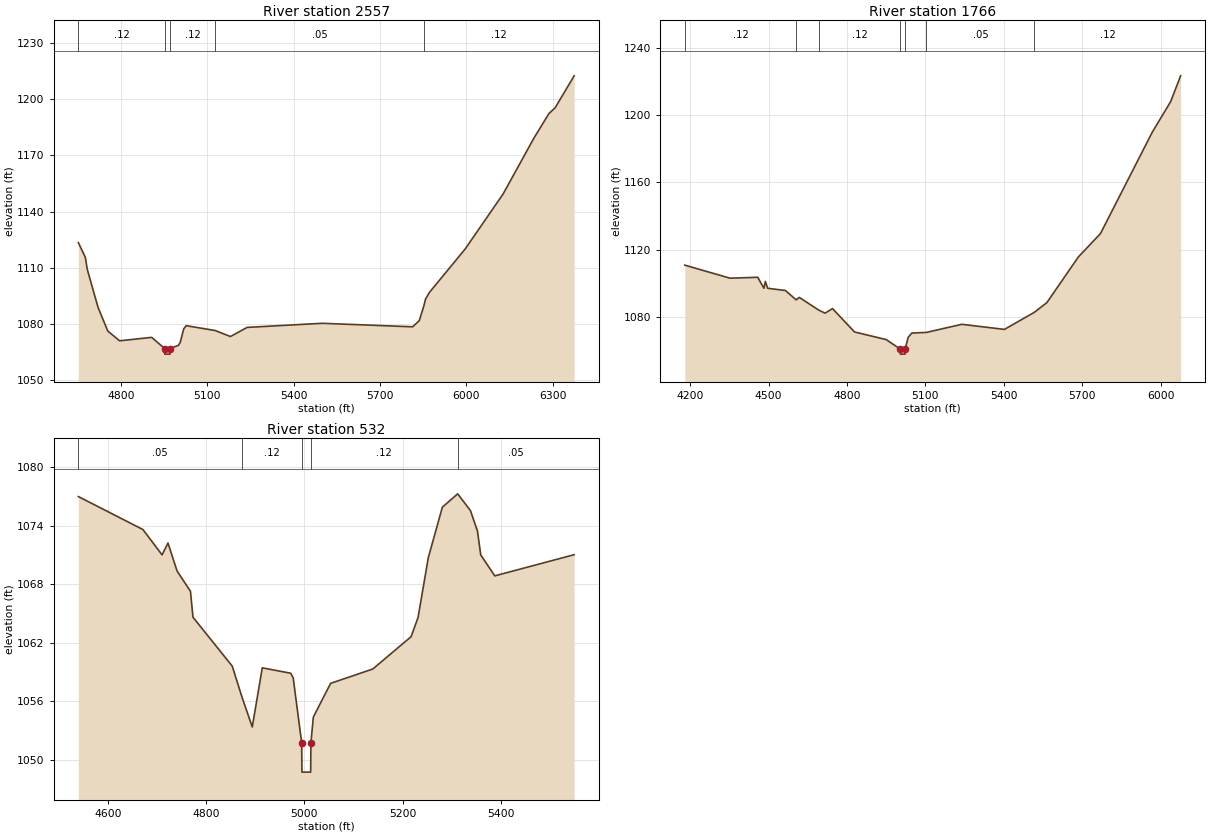
Type RM Length L Ch R = 1,2557,791,791,791
BEGIN DESCRIPTION:
WOLF HOLLOW CREEK 5.0
END DESCRIPTION:
XS GIS Cut Line= 3
      2853005.67     10197753.16      2853079.50     10197414.00
      2854255.66     10196703.12
#Sta/Elev= 30
  4652.9 1123.48  4677.5 1115.50  4683.7 1109.35  4721.5 1088.83  4755.3 1076.25
  4796.2 1071.07  4907.6 1072.90  4952.5 1066.96  4953.0 1063.96  4970.7 1063.96
  4971.2 1066.96  5000.0 1068.63  5006.4 1070.04  5018.9 1077.50  5027.7 1079.13
  5128.3 1076.55  5181.0 1073.35  5239.2 1078.22  5499.3 1080.41  5813.5 1078.54
  5836.8 1081.87  5853.6 1090.28  5858.2 1093.31  5871.9 1096.90  5996.0 1120.07
  6127.9 1149.47  6234.6 1179.21  6287.0 1192.37  6308.4 1195.43  6374.3 1212.45
#Mann=5,-1,0
  4652.9    0.12       0  4952.5    0.07       0  4971.2    0.12       0
  5128.3    0.05       0  5853.6    0.12       0
Bank Sta=4952.5,4971.2
Exp/Cntr=0.3,0.1

Type RM Length L Ch R = 1,1766,1234,1234,1234
BEGIN DESCRIPTION:
Mapping XS 9b5bc74e
END DESCRIPTION:
XS GIS Cut Line= 4
      2853013.02     10198035.42      2853481.79     10197840.10
      2854002.63     10197358.33      2854483.66     10196877.30
#Sta/Elev= 30
  4179.4 1110.87  4352.3 1103.13  4458.5 1103.66  4482.3 1097.15  4487.7 1101.22
  4496.5 1097.14  4564.6 1095.82  4605.4 1090.27  4617.7 1091.71  4691.3 1084.24
  4716.3 1082.35  4744.6 1085.08  4829.1 1071.19  4949.9 1066.69  5004.1 1061.04
  5004.6 1058.04  5022.3 1058.04  5022.8 1061.04  5034.4 1068.08  5048.6 1070.55
  5104.1 1070.93  5239.6 1075.75  5402.6 1072.72  5516.7 1082.81  5565.2 1088.63
  5685.4 1115.68  5770.3 1129.62  5968.3 1189.74  6039.0 1207.99  6077.0 1223.26
#Mann=7,-1,0
  4179.4    0.12       0  4605.4    0.05       0  4691.3    0.12       0
  5004.1    0.07       0  5022.8    0.12       0  5104.1    0.05       0
  5516.7    0.12       0
Bank Sta=5004.1,5022.8
Exp/Cntr=0.3,0.1

Type RM Length L Ch R = 1,532,0,0,0
BEGIN DESCRIPTION:
WOLF HOLLOW CREEK 1.0
END DESCRIPTION:
XS GIS Cut Line= 3
      2853898.48     10198543.22      2854349.75     10198453.00
      2854703.37     10198032.80
#Sta/Elev= 30
  4539.8 1076.97  4671.3 1073.59  4710.3 1070.99  4722.3 1072.21  4740.9 1069.33
  4768.1 1067.26  4773.2 1064.60  4853.1 1059.59  4873.0 1056.41  4893.9 1053.35
  4914.3 1059.41  4972.1 1058.86  4977.2 1058.39  4994.5 1051.72  4995.0 1048.72
  5012.8 1048.72  5013.3 1051.72  5018.2 1054.36  5053.4 1057.82  5139.2 1059.29
  5217.2 1062.60  5231.5 1064.59  5252.3 1070.71  5280.9 1075.88  5312.1 1077.25
  5338.1 1075.53  5352.4 1073.43  5359.0 1070.99  5387.6 1068.84  5549.2 1071.01
#Mann=5,-1,0
  4539.8    0.05       0  4873.0    0.12       0  4994.5    0.07       0
  5013.3    0.12       0  5312.1    0.05       0
Bank Sta=4994.5,5013.3
Exp/Cntr=0.3,0.1

Chan Stop Cuts=-1