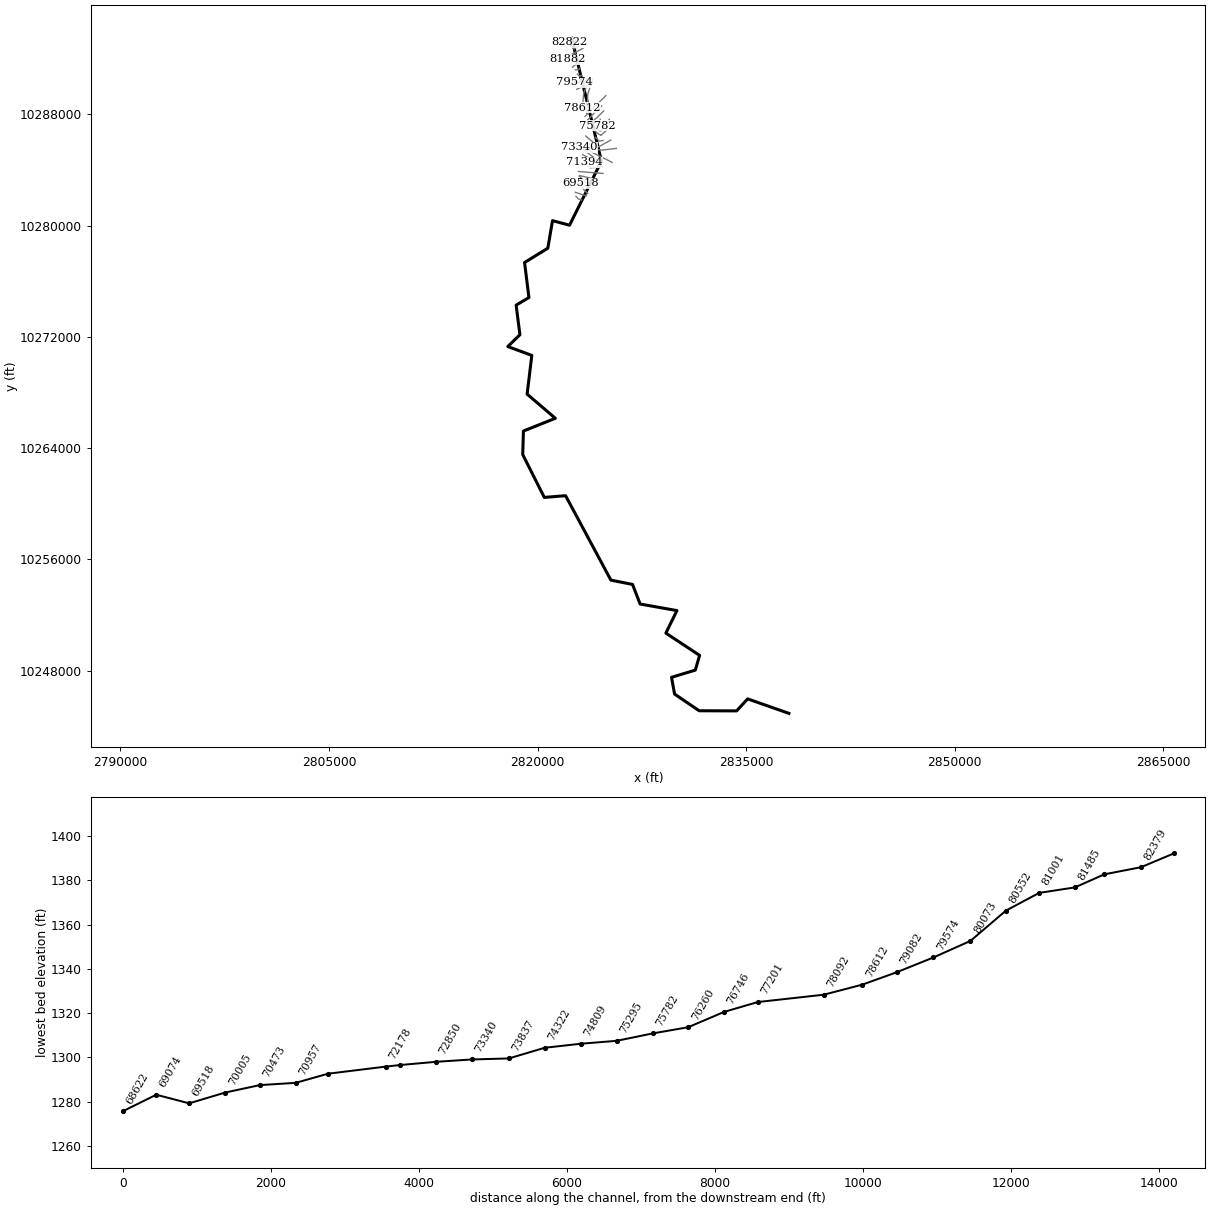
--- WRIGHTS CREEK.prj (project) ---

Proj Title=WRIGHTS CREEK Base Level Engineering
Current Plan=p01
Default Exp/Contr=0.3,0.1
English Units
Geom File=g01
Flow File=f01
Plan File=p01
BEGIN DESCRIPTION:
WRIGHTS CREEK
END DESCRIPTION:

--- WRIGHTS CREEK.p01 (plan) ---

Plan Title=Multiple Run
Short Identifier=Multiple
Geom File=g01
Flow File=f01
Subcritical Flow
K Sum by GR= 0
Std Step Tol= 0.01
Critical Tol= 0.01
Num of Std Step Trials= 20
Max Error Tol= 0.3
Flow Tol Ratio= 0.001
Split Flow NTrial= 30
Split Flow Tol= 0.02
Split Flow Ratio= 0.02
Log Output Level= 0
Friction Slope Method= 1
Unsteady Friction Slope Method= 2
Unsteady Bridges Friction Slope Method= 1
Parabolic Critical Depth
Global Vel Dist=  1 , 1 , 1
Global Log Level= 0
CheckData=True
Encroach Param= -1, 0, 0, 0
BEGIN DESCRIPTION:
Multiple Run
END DESCRIPTION:

--- WRIGHTS CREEK.f01 (steady flow) ---

Flow Title=Multiple
Number of Profiles=7
Profile Names=10-year,25-year,50-year,1pct_min,100-year,1pct_plu,500-year
River Rch & RM= WRIGHTS CREEK,Reach-1,82822
      65     122     190      98     296     893     773
River Rch & RM= WRIGHTS CREEK,Reach-1,73340
     138     291     475     255     770    2326    2159
River Rch & RM= WRIGHTS CREEK,Reach-1,67169
     167     362     597     324     977    2950    2780
River Rch & RM= WRIGHTS CREEK,Reach-1,62334
     179     390     646     351    1060    3200    3030
River Rch & RM= WRIGHTS CREEK,Reach-1,61350
     198     435     723     394    1189    3592    3422
River Rch & RM= WRIGHTS CREEK,Reach-1,59530
     221     489     816     446    1348    4070    3904
River Rch & RM= WRIGHTS CREEK,Reach-1,55515
     276     621    1044     575    1737    5244    5099
River Rch & RM= WRIGHTS CREEK,Reach-1,43716
     337     765    1297     718    2169    6551    6440
River Rch & RM= WRIGHTS CREEK,Reach-1,40762
     371     848    1441     801    2418    7303    7216
River Rch & RM= WRIGHTS CREEK,Reach-1,39113
     386     884    1504     837    2527    7630    7555
River Rch & RM= WRIGHTS CREEK,Reach-1,33808
     408     939    1600     891    2692    8128    8072
River Rch & RM= WRIGHTS CREEK,Reach-1,31585
     419     966    1647     918    2772    8372    8325
River Rch & RM= WRIGHTS CREEK,Reach-1,30631
     462    1070    1831    1023    3089    9329    9321
River Rch & RM= WRIGHTS CREEK,Reach-1,27469
     476    1104    1890    1057    3192    9640    9645
River Rch & RM= WRIGHTS CREEK,Reach-1,25685
     497    1155    1979    1108    3346   10104   10130
River Rch & RM= WRIGHTS CREEK,Reach-1,23361
     504    1171    2007    1124    3395   10252   10285
River Rch & RM= WRIGHTS CREEK,Reach-1,19927
     541    1263    2170    1217    3676   11101   11174
River Rch & RM= WRIGHTS CREEK,Reach-1,10404
     603    1413    2434    1369    4133   12482   12625
River Rch & RM= WRIGHTS CREEK,Reach-1,6075
     618    1451    2502    1408    4251   12838   13000
Boundary for River Rch & Prof#=WRIGHTS CREEK,Reach-1,1
Up Type=0
Dn Type=3
Dn Slope=0.005
Boundary for River Rch & Prof#=WRIGHTS CREEK,Reach-1,2
Up Type=0
Dn Type=3
Dn Slope=0.005
Boundary for River Rch & Prof#=WRIGHTS CREEK,Reach-1,3
Up Type=0
Dn Type=3
Dn Slope=0.005
Boundary for River Rch & Prof#=WRIGHTS CREEK,Reach-1,4
Up Type=0
Dn Type=3
Dn Slope=0.005
Boundary for River Rch & Prof#=WRIGHTS CREEK,Reach-1,5
Up Type=0
Dn Type=3
Dn Slope=0.005
Boundary for River Rch & Prof#=WRIGHTS CREEK,Reach-1,6
Up Type=0
Dn Type=3
Dn Slope=0.005
Boundary for River Rch & Prof#=WRIGHTS CREEK,Reach-1,7
Up Type=0
Dn Type=3
Dn Slope=0.005

--- WRIGHTS CREEK.g01 (geometry) ---

Geom Title=Existing Conditions

River Reach=WRIGHTS CREEK,Reach-1
Reach XY= 30
      2822450.00     10293473.00      2824588.00     10284643.00
      2822291.25     10280034.00      2821067.25     10280362.00
      2820730.25     10278380.00      2819058.75     10277351.00
      2819372.00     10274833.00      2818451.75     10274287.00
      2818724.00     10272157.00      2817852.50     10271310.00
      2819579.50     10270672.00      2819242.25     10267887.00
      2821272.25     10266150.00      2818977.25     10265233.00
      2818926.00     10263541.00      2820477.75     10260460.00
      2822009.25     10260583.00      2825266.75     10254510.00
      2826821.50     10254203.00      2827369.00     10252793.00
      2830016.00     10252321.00      2829219.50     10250701.00
      2831646.50     10249100.00      2831337.75     10248040.00
      2829625.50     10247522.00      2829847.75     10246318.00
      2831613.75     10245117.00      2834307.50     10245108.00
      2835102.50     10245971.00      2838068.50     10244929.00

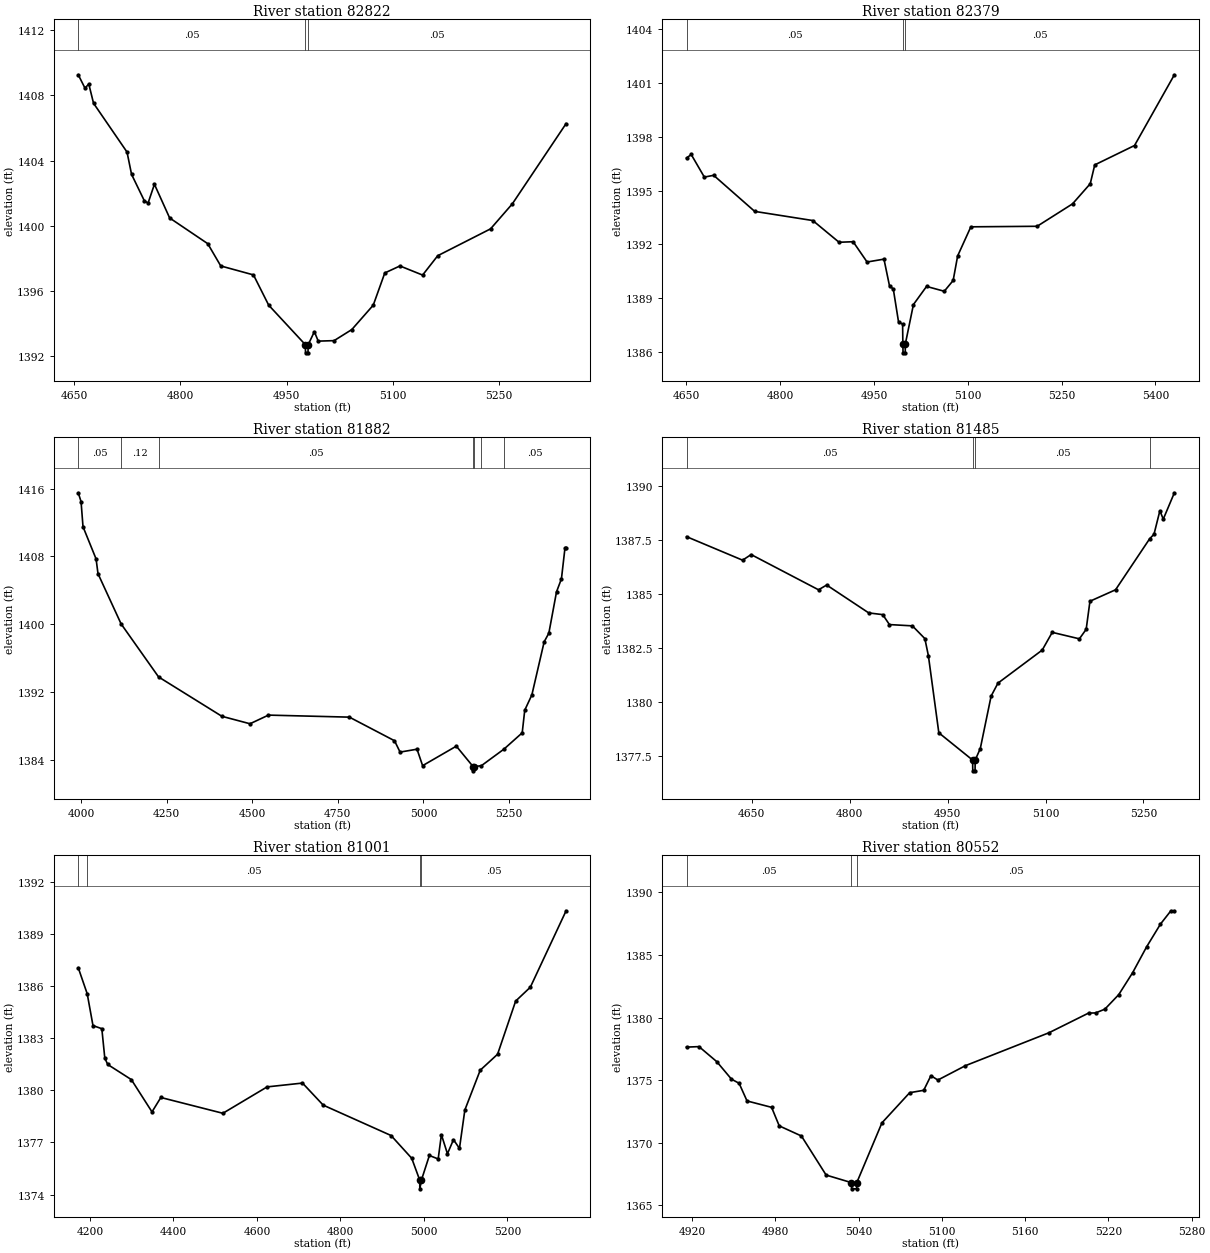
Type RM Length L Ch R = 1,82822,443,443,443
BEGIN DESCRIPTION:
WRIGHTS CREEK 154.0
END DESCRIPTION:
XS GIS Cut Line= 3
      2822755.70     10293403.15      2822628.75     10293083.00
      2822305.66     10293203.12
#Sta/Elev= 30
  4655.6 1409.27  4665.1 1408.45  4670.5 1408.70  4677.2 1407.52  4724.5 1404.52
  4730.9 1403.15  4748.8 1401.54  4754.2 1401.38  4763.2 1402.54  4784.7 1400.47
  4838.5 1398.89  4856.9 1397.52  4903.1 1396.97  4924.6 1395.11  4976.4 1392.68
  4976.6 1392.18  4980.1 1392.18  4980.4 1392.68  4989.1 1393.48  4994.6 1392.90
  5017.0 1392.93  5042.0 1393.61  5072.3 1395.11  5088.6 1397.09  5110.0 1397.52
  5142.0 1396.96  5163.4 1398.15  5238.0 1399.80  5268.8 1401.34  5344.7 1406.27
#Mann=3,-1,0
  4655.6    0.05       0  4976.4    0.03       0  4980.4    0.05       0
Bank Sta=4976.4,4980.4
Exp/Cntr=0.3,0.1

Type RM Length L Ch R = 1,82379,497,497,497
BEGIN DESCRIPTION:
WRIGHTS CREEK 153.0
END DESCRIPTION:
XS GIS Cut Line= 3
      2822905.71     10292903.13      2822616.75     10292706.00
      2822305.65     10293003.14
#Sta/Elev= 30
  4650.2 1396.81  4657.7 1397.01  4678.7 1395.75  4693.6 1395.85  4759.2 1393.84
  4852.1 1393.33  4894.1 1392.12  4916.6 1392.15  4938.9 1391.02  4965.9 1391.18
  4974.8 1389.68  4980.8 1389.52  4989.2 1387.68  4995.7 1387.56  4996.1 1386.46
  4996.4 1385.96  4999.9 1385.96  5000.1 1386.46  5013.0 1388.65  5034.0 1389.66
  5062.3 1389.39  5076.5 1389.99  5083.7 1391.36  5104.8 1392.98  5210.8 1393.01
  5267.4 1394.26  5295.7 1395.38  5302.9 1396.43  5366.5 1397.51  5430.2 1401.45
#Mann=3,-1,0
  4650.2    0.05       0  4996.1    0.03       0  5000.1    0.05       0
Bank Sta=4996.1,5000.1
Exp/Cntr=0.3,0.1

Type RM Length L Ch R = 1,81882,397,397,397
BEGIN DESCRIPTION:
WRIGHTS CREEK 152.0
END DESCRIPTION:
XS GIS Cut Line= 3
      2823255.72     10292753.13      2822366.50     10292278.00
      2822105.70     10291953.13
#Sta/Elev= 30
  3991.8 1415.51  4000.0 1414.47  4005.7 1411.51  4043.9 1407.71  4049.5 1405.97
  4117.0 1400.05  4226.4 1393.80  4411.3 1389.16  4493.4 1388.28  4547.4 1389.30
  4783.7 1389.06  4915.4 1386.28  4931.7 1384.94  4981.2 1385.28  4997.5 1383.34
  5096.0 1385.64  5145.0 1383.23  5145.2 1382.73  5149.0 1383.23  5169.3 1383.34
  5235.1 1385.29  5288.4 1387.21  5295.8 1389.88  5316.6 1391.68  5352.5 1397.94
  5366.2 1398.96  5388.6 1403.83  5403.0 1405.37  5413.4 1409.04  5416.6 1409.04
#Mann=7,-1,0
  3991.8    0.05       0  4117.0    0.12       0  4226.4    0.05       0
  5145.0    0.03       0  5149.0    0.05       0  5169.3    0.12       0
  5235.1    0.05       0
Bank Sta=5145,5149
Exp/Cntr=0.3,0.1

Type RM Length L Ch R = 1,81485,484,484,484
BEGIN DESCRIPTION:
WRIGHTS CREEK 151.0
END DESCRIPTION:
XS GIS Cut Line= 3
      2822705.67     10292353.08      2822541.75     10291934.00
      2822255.67     10291853.11
#Sta/Elev= 30
  4550.0 1387.67  4635.9 1386.58  4649.0 1386.84  4752.2 1385.21  4764.7 1385.43
  4829.1 1384.14  4850.6 1384.06  4860.8 1383.60  4896.0 1383.54  4915.1 1382.95
  4920.5 1382.16  4936.5 1378.59  4988.2 1377.33  4988.5 1376.83  4992.0 1376.83
  4992.2 1377.33  5000.0 1377.86  5016.6 1380.29  5027.1 1380.89  5094.9 1382.42
  5110.2 1383.24  5151.8 1382.94  5162.2 1383.38  5168.0 1384.68  5207.2 1385.21
  5259.4 1387.57  5266.1 1387.78  5275.1 1388.87  5280.3 1388.48  5297.3 1389.70
#Mann=4,-1,0
  4550.0    0.05       0  4988.2    0.03       0  4992.2    0.05       0
  5259.4    0.12       0
Bank Sta=4988.2,4992.2
Exp/Cntr=0.3,0.1

Type RM Length L Ch R = 1,81001,449,449,449
BEGIN DESCRIPTION:
WRIGHTS CREEK 150.0
END DESCRIPTION:
XS GIS Cut Line= 3
      2823355.66     10292203.08      2822772.50     10291615.00
      2822505.70     10291403.12
#Sta/Elev= 30
  4171.8 1387.06  4193.3 1385.56  4207.1 1383.73  4228.3 1383.55  4235.4 1381.86
  4242.4 1381.49  4299.0 1380.62  4348.5 1378.76  4369.7 1379.59  4518.3 1378.68
  4624.3 1380.20  4709.1 1380.42  4758.7 1379.15  4921.3 1377.40  4970.8 1376.09
  4990.0 1374.83  4990.2 1374.33  4994.0 1374.83  5013.1 1376.25  5034.2 1376.05
  5041.9 1377.45  5056.4 1376.35  5070.8 1377.16  5085.2 1376.66  5098.1 1378.87
  5134.9 1381.16  5176.5 1382.08  5219.8 1385.14  5255.0 1385.94  5340.7 1390.34
#Mann=4,-1,0
  4171.8    0.12       0  4193.3    0.05       0  4990.0    0.03       0
  4994.0    0.05       0
Bank Sta=4990,4994
Exp/Cntr=0.3,0.1

Type RM Length L Ch R = 1,80552,479,479,479
BEGIN DESCRIPTION:
WRIGHTS CREEK 149.0
END DESCRIPTION:
XS GIS Cut Line= 3
      2823005.67     10291303.07      2822972.25     10291226.00
      2822705.73     10291203.12
#Sta/Elev= 30
  4916.0 1377.64  4925.0 1377.68  4937.8 1376.48  4948.4 1375.08  4953.9 1374.75
  4959.6 1373.34  4977.3 1372.83  4982.8 1371.35  4998.8 1370.54  5016.6 1367.42
  5034.7 1366.82  5035.0 1366.32  5038.5 1366.32  5038.7 1366.82  5056.8 1371.59
  5076.8 1374.00  5086.9 1374.19  5092.1 1375.36  5097.1 1375.01  5117.0 1376.16
  5177.2 1378.79  5205.7 1380.36  5210.7 1380.37  5217.4 1380.67  5227.4 1381.83
  5237.4 1383.58  5247.5 1385.65  5257.5 1387.47  5265.0 1388.53  5267.5 1388.53
#Mann=3,-1,0
  4916.0    0.05       0  5034.7    0.03       0  5038.7    0.05       0
Bank Sta=5034.7,5038.7
Exp/Cntr=0.3,0.1

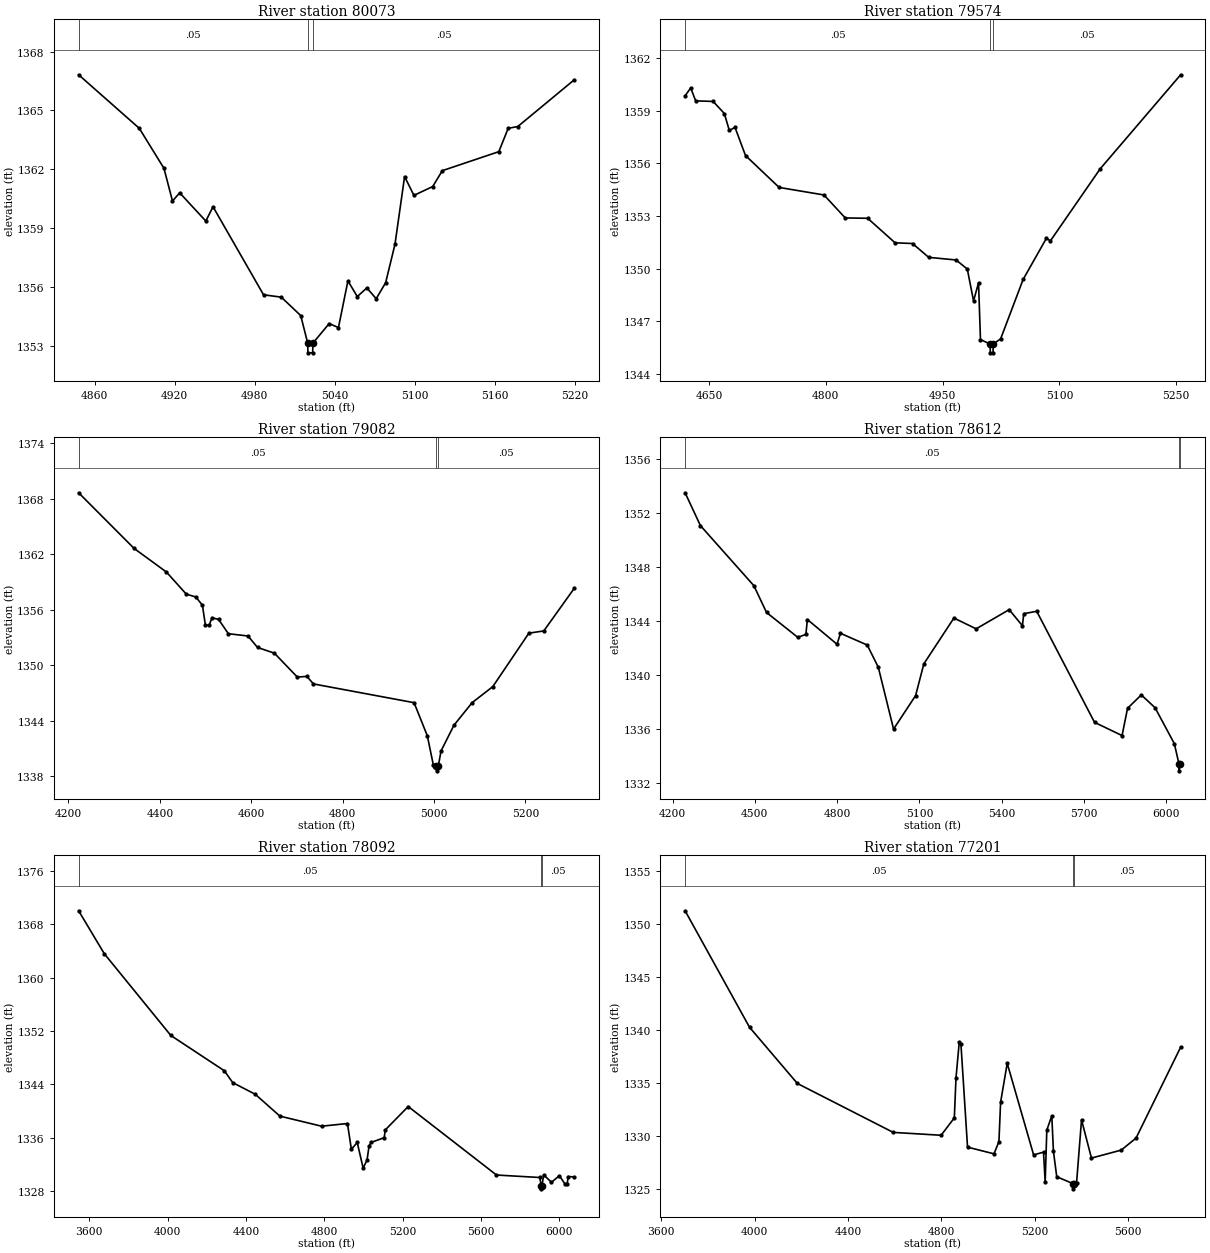
Type RM Length L Ch R = 1,80073,499,499,499
BEGIN DESCRIPTION:
WRIGHTS CREEK 148.0
END DESCRIPTION:
XS GIS Cut Line= 3
      2823155.67     10290803.11      2823013.25     10290750.00
      2822855.69     10290903.11
#Sta/Elev= 30
  4848.0 1366.82  4893.5 1364.09  4912.0 1362.05  4918.4 1360.38  4923.8 1360.80
  4943.4 1359.36  4948.8 1360.09  4986.7 1355.60  5000.0 1355.48  5014.6 1354.54
  5019.8 1353.14  5020.0 1352.64  5023.5 1352.64  5023.8 1353.14  5035.9 1354.13
  5042.9 1353.93  5050.0 1356.31  5057.0 1355.51  5064.2 1355.95  5071.2 1355.40
  5078.3 1356.22  5085.3 1358.18  5092.5 1361.63  5099.5 1360.67  5113.6 1361.12
  5120.8 1361.93  5163.2 1362.90  5170.2 1364.09  5177.4 1364.18  5219.7 1366.56
#Mann=3,-1,0
  4848.0    0.05       0  5019.8    0.05       0  5023.8    0.05       0
Bank Sta=5019.8,5023.8
Exp/Cntr=0.3,0.1

Type RM Length L Ch R = 1,79574,492,492,492
BEGIN DESCRIPTION:
WRIGHTS CREEK 147.0
END DESCRIPTION:
XS GIS Cut Line= 3
      2823205.68     10290503.11      2822908.50     10290265.00
      2822655.66     10290303.12
#Sta/Elev= 30
  4619.2 1359.86  4626.4 1360.31  4632.8 1359.57  4655.2 1359.54  4669.6 1358.85
  4676.0 1357.88  4683.3 1358.06  4696.8 1356.45  4740.0 1354.63  4797.6 1354.20
  4824.9 1352.89  4853.7 1352.87  4888.9 1351.47  4911.3 1351.43  4932.1 1350.64
  4967.3 1350.49  4981.7 1349.97  4989.7 1348.15  4996.1 1349.19  4998.6 1345.95
  5011.0 1345.69  5011.2 1345.19  5014.7 1345.19  5015.0 1345.69  5024.5 1345.99
  5053.4 1349.38  5083.3 1351.73  5088.4 1351.58  5152.3 1355.69  5255.7 1361.06
#Mann=3,-1,0
  4619.2    0.05       0  5011.0    0.05       0  5015.0    0.05       0
Bank Sta=5011,5015
Exp/Cntr=0.3,0.1

Type RM Length L Ch R = 1,79082,470,470,470
BEGIN DESCRIPTION:
WRIGHTS CREEK 146.0
END DESCRIPTION:
XS GIS Cut Line= 3
      2823555.69     10290553.11      2823082.25     10289936.00
      2822805.72     10289803.13
#Sta/Elev= 30
  4222.2 1368.66  4343.7 1362.63  4414.3 1360.08  4457.9 1357.68  4478.7 1357.38
  4493.2 1356.48  4499.5 1354.36  4507.7 1354.29  4514.1 1355.14  4528.6 1354.94
  4549.9 1353.40  4592.9 1353.15  4613.8 1351.91  4650.7 1351.29  4700.9 1348.70
  4721.7 1348.78  4736.2 1347.96  4956.4 1345.93  4985.4 1342.34  4998.7 1339.15
  5005.3 1339.05  5005.5 1338.55  5009.3 1339.05  5015.5 1340.71  5043.7 1343.49
  5083.4 1345.93  5128.7 1347.67  5207.7 1353.46  5240.3 1353.70  5306.8 1358.30
#Mann=3,-1,0
  4222.2    0.05       0  5005.3    0.05       0  5009.3    0.05       0
Bank Sta=5005.3,5009.3
Exp/Cntr=0.3,0.1

Type RM Length L Ch R = 1,78612,520,520,520
BEGIN DESCRIPTION:
Mapping XS d1c06bb4
END DESCRIPTION:
XS GIS Cut Line= 3
      2823615.12     10290216.45      2823311.28     10289554.52
      2823224.47     10288480.26
#Sta/Elev= 30
  4245.7 1353.47  4301.6 1351.04  4496.5 1346.59  4542.5 1344.61  4656.5 1342.77
  4685.9 1342.99  4691.4 1344.09  4799.5 1342.26  4811.9 1343.07  4909.6 1342.20
  4949.8 1340.56  5005.5 1335.98  5085.8 1338.46  5115.9 1340.81  5225.5 1344.20
  5306.5 1343.40  5426.9 1344.82  5475.1 1343.63  5480.1 1344.52  5527.2 1344.70
  5737.9 1336.48  5838.3 1335.50  5858.3 1337.52  5908.5 1338.51  5958.6 1337.56
  6028.9 1334.90  6045.8 1333.39  6046.1 1332.89  6049.8 1333.39  6051.8 1333.39
#Mann=3,-1,0
  4245.7    0.05       0  6045.8    0.05       0  6049.8    0.05       0
Bank Sta=6045.8,6049.8
Exp/Cntr=0.3,0.1

Type RM Length L Ch R = 1,78092,891,891,891
BEGIN DESCRIPTION:
Mapping XS dfd84704
END DESCRIPTION:
XS GIS Cut Line= 4
      2823951.47     10290531.07      2823604.25     10289456.87
      2823582.55     10288762.42      2823528.33     10288057.61
#Sta/Elev= 30
  3545.4 1370.03  3676.3 1363.60  4016.2 1351.34  4289.4 1346.05  4332.5 1344.27
  4447.1 1342.53  4573.2 1339.25  4785.8 1337.74  4918.2 1338.14  4938.2 1334.28
  4968.2 1335.30  4998.2 1331.46  5018.2 1332.66  5028.3 1334.72  5038.3 1335.30
  5106.0 1336.02  5111.0 1337.17  5228.4 1340.69  5679.3 1330.42  5900.0 1330.05
  5908.0 1328.85  5908.2 1328.35  5912.0 1328.85  5920.0 1330.44  5960.2 1329.34
  6000.3 1330.32  6030.4 1329.02  6040.4 1329.13  6045.4 1330.19  6076.0 1330.14
#Mann=3,-1,0
  3545.4    0.05       0  5908.0    0.03       0  5912.0    0.05       0
Bank Sta=5908,5912
Exp/Cntr=0.3,0.1

Type RM Length L Ch R = 1,77201,455,455,455
BEGIN DESCRIPTION:
WRIGHTS CREEK 142.0
END DESCRIPTION:
XS GIS Cut Line= 3
      2824905.68     10289353.11      2823981.75     10288442.00
      2823405.68     10287853.11
#Sta/Elev= 30
  3702.4 1351.25  3978.2 1340.27  4183.2 1334.97  4593.4 1330.36  4798.4 1330.09
  4855.0 1331.73  4862.1 1335.50  4876.2 1338.89  4883.3 1338.67  4911.5 1328.97
  5024.8 1328.34  5045.9 1329.49  5053.1 1333.21  5081.4 1336.87  5194.4 1328.24
  5236.8 1328.50  5243.9 1325.69  5250.9 1330.58  5272.2 1331.92  5279.2 1328.59
  5293.4 1326.18  5362.1 1325.54  5362.3 1325.04  5366.1 1325.54  5378.2 1325.58
  5399.5 1331.54  5442.0 1327.94  5569.3 1328.69  5632.8 1329.82  5823.8 1338.39
#Mann=3,-1,0
  3702.4    0.05       0  5362.1    0.05       0  5366.1    0.05       0
Bank Sta=5362.1,5366.1
Exp/Cntr=0.3,0.1

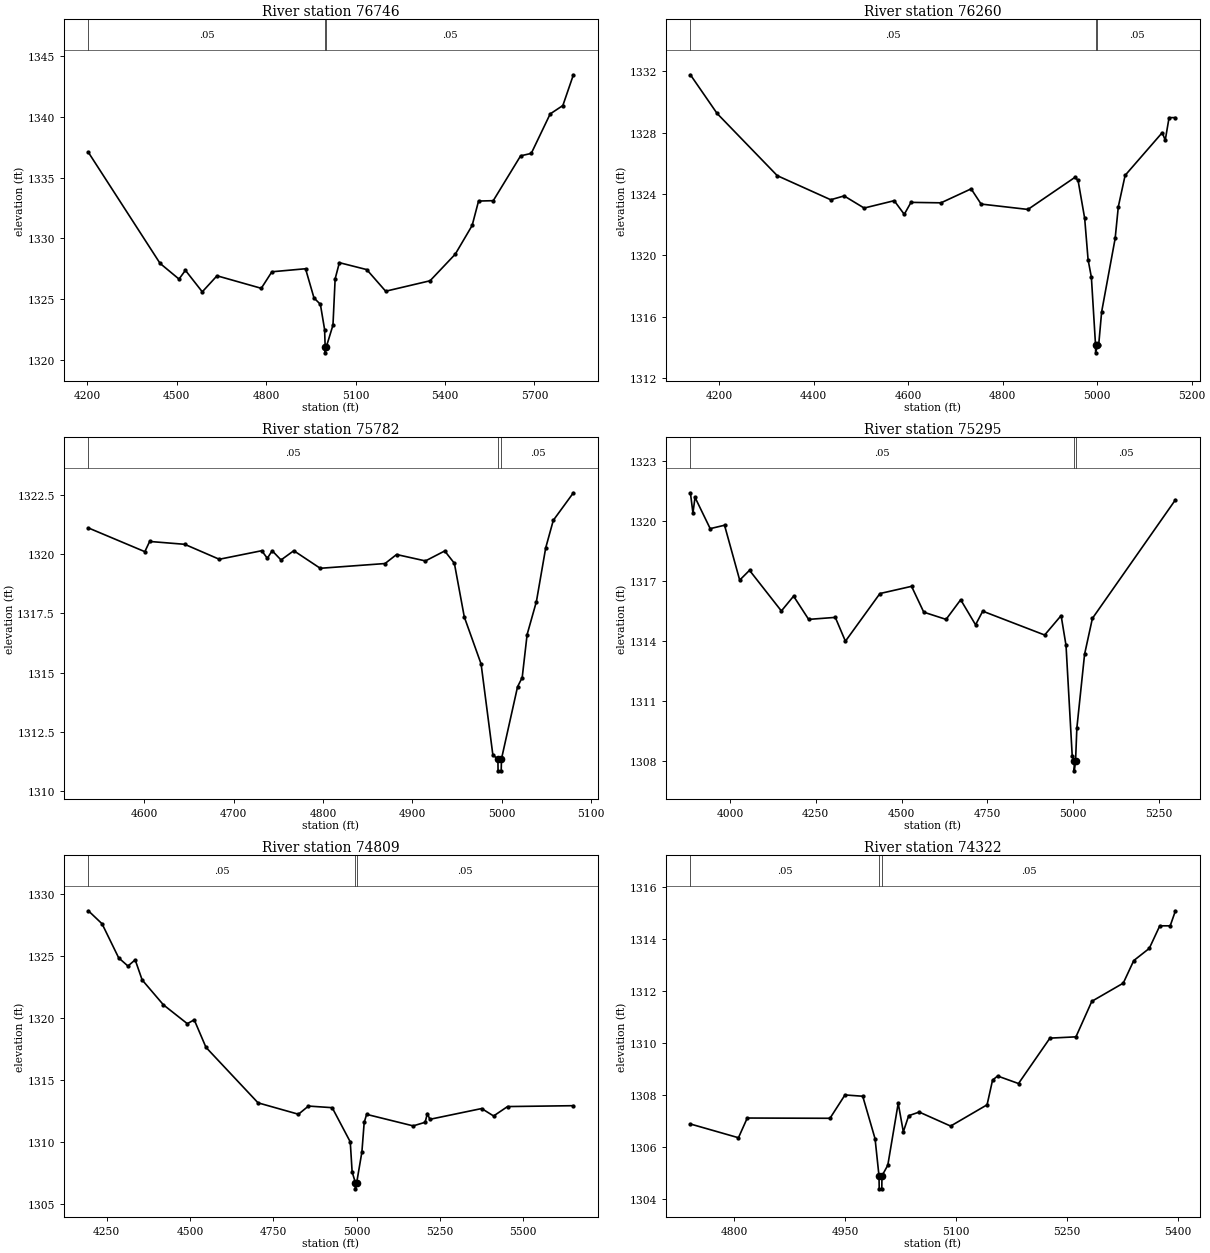
Type RM Length L Ch R = 1,76746,486,486,486
BEGIN DESCRIPTION:
WRIGHTS CREEK 141.0
END DESCRIPTION:
XS GIS Cut Line= 3
      2824605.72     10288603.14      2824025.00     10288058.00
      2823455.66     10287453.09
#Sta/Elev= 30
  4203.5 1337.09  4444.1 1327.95  4507.6 1326.66  4529.1 1327.38  4585.7 1325.61
  4635.1 1326.93  4783.6 1325.90  4819.2 1327.26  4932.1 1327.51  4960.4 1325.11
  4981.9 1324.58  4996.0 1322.51  4997.9 1321.09  4998.2 1320.59  5001.9 1321.09
  5024.1 1322.87  5031.4 1326.68  5045.6 1328.01  5137.4 1327.44  5200.9 1325.66
  5349.8 1326.52  5434.4 1328.71  5491.0 1331.07  5512.5 1333.08  5561.8 1333.11
  5653.6 1336.80  5689.3 1337.00  5752.8 1340.25  5795.3 1340.94  5830.7 1343.47
#Mann=3,-1,0
  4203.5    0.05       0  4997.9    0.05       0  5001.9    0.05       0
Bank Sta=4997.9,5001.9
Exp/Cntr=0.3,0.1

Type RM Length L Ch R = 1,76260,478,478,478
BEGIN DESCRIPTION:
WRIGHTS CREEK 140.0
END DESCRIPTION:
XS GIS Cut Line= 3
      2824755.68     10288253.10      2824135.50     10287656.00
      2824005.72     10287553.14
#Sta/Elev= 30
  4139.1 1331.77  4195.6 1329.25  4322.9 1325.20  4436.1 1323.63  4464.4 1323.88
  4506.8 1323.09  4570.4 1323.57  4591.7 1322.68  4605.9 1323.46  4669.4 1323.43
  4733.2 1324.34  4754.3 1323.35  4853.4 1323.00  4952.4 1325.08  4959.4 1324.91
  4973.5 1322.42  4980.7 1319.73  4987.7 1318.58  4996.5 1314.16  4996.7 1313.66
  5000.5 1314.16  5003.1 1314.16  5009.4 1316.33  5038.0 1321.11  5044.7 1323.18
  5059.1 1325.22  5137.6 1328.00  5144.0 1327.51  5152.1 1328.98  5165.6 1328.98
#Mann=3,-1,0
  4139.1    0.05       0  4996.5    0.05       0  5000.5    0.05       0
Bank Sta=4996.5,5000.5
Exp/Cntr=0.3,0.1

Type RM Length L Ch R = 1,75782,487,487,487
BEGIN DESCRIPTION:
WRIGHTS CREEK 139.0
END DESCRIPTION:
XS GIS Cut Line= 3
      2824505.70     10287653.15      2824333.25     10287224.00
      2824255.71     10287203.12
#Sta/Elev= 30
  4537.5 1321.10  4600.7 1320.10  4606.1 1320.53  4645.3 1320.41  4684.0 1319.78
  4731.5 1320.14  4737.8 1319.82  4743.2 1320.14  4753.1 1319.75  4767.4 1320.14
  4797.0 1319.40  4869.5 1319.60  4882.4 1319.98  4914.7 1319.71  4936.3 1320.13
  4947.1 1319.61  4958.2 1317.35  4977.0 1315.37  4990.2 1311.53  4995.8 1311.37
  4996.0 1310.87  4999.5 1310.87  4999.8 1311.37  5017.8 1314.41  5023.0 1314.80
  5028.5 1316.61  5038.9 1318.00  5049.3 1320.26  5057.8 1321.42  5080.3 1322.58
#Mann=3,-1,0
  4537.5    0.05       0  4995.8    0.05       0  4999.8    0.05       0
Bank Sta=4995.8,4999.8
Exp/Cntr=0.3,0.1

Type RM Length L Ch R = 1,75295,486,486,486
BEGIN DESCRIPTION:
WRIGHTS CREEK 138.0
END DESCRIPTION:
XS GIS Cut Line= 4
      2825155.69     10287653.11      2824549.20     10286808.32
      2824475.75     10286826.00      2824205.67     10286953.12
#Sta/Elev= 30
  3884.5 1321.40  3891.9 1320.39  3898.0 1321.17  3942.2 1319.61  3984.0 1319.78
  4028.2 1317.04  4056.8 1317.53  4149.7 1315.50  4185.3 1316.24  4229.2 1315.08
  4306.9 1315.18  4336.4 1313.99  4437.0 1316.37  4529.2 1316.73  4564.8 1315.44
  4629.8 1315.08  4672.4 1316.06  4715.8 1314.81  4736.7 1315.49  4917.2 1314.30
  4965.2 1315.27  4979.5 1313.78  4997.5 1308.28  5003.3 1308.02  5003.5 1307.52
  5007.3 1308.02  5011.1 1309.66  5033.6 1313.34  5056.4 1315.13  5298.5 1321.05
#Mann=3,-1,0
  3884.5    0.05       0  5003.3    0.05       0  5007.3    0.05       0
Bank Sta=5003.3,5007.3
Exp/Cntr=0.3,0.1

Type RM Length L Ch R = 1,74809,487,487,487
BEGIN DESCRIPTION:
WRIGHTS CREEK 137.0
END DESCRIPTION:
XS GIS Cut Line= 5
      2823864.00     10287018.96      2824367.24     10286604.00
      2824501.75     10286531.00      2824546.15     10286489.13
      2824982.28     10286885.25
#Sta/Elev= 30
  4194.7 1328.64  4235.8 1327.59  4285.7 1324.84  4313.5 1324.18  4335.2 1324.68
  4356.1 1323.06  4419.9 1321.05  4491.6 1319.53  4512.4 1319.84  4547.6 1317.62
  4703.9 1313.14  4825.1 1312.22  4855.1 1312.88  4926.4 1312.75  4980.6 1309.99
  4986.2 1307.57  4995.9 1306.70  4996.1 1306.20  4999.9 1306.70  5015.5 1309.17
  5022.4 1311.56  5029.7 1312.21  5169.4 1311.28  5205.2 1311.57  5212.0 1312.28
  5219.4 1311.81  5374.9 1312.68  5410.7 1312.08  5452.6 1312.84  5650.2 1312.91
#Mann=3,-1,0
  4194.7    0.05       0  4995.9    0.03       0  4999.9    0.05       0
Bank Sta=4995.9,4999.9
Exp/Cntr=0.3,0.1

Type RM Length L Ch R = 1,74322,485,485,485
BEGIN DESCRIPTION:
WRIGHTS CREEK 136.0
END DESCRIPTION:
XS GIS Cut Line= 3
      2824701.23     10286130.69      2824446.25     10286083.00
      2824155.70     10286353.10
#Sta/Elev= 30
  4740.6 1306.88  4805.6 1306.35  4817.5 1307.11  4929.4 1307.10  4949.7 1308.00
  4973.7 1307.95  4990.4 1306.31  4995.7 1304.88  4996.0 1304.38  4999.5 1304.38
  4999.7 1304.88  5007.6 1305.29  5021.7 1307.68  5028.6 1306.58  5035.9 1307.20
  5050.1 1307.34  5092.6 1306.80  5141.9 1307.62  5149.3 1308.57  5156.1 1308.73
  5184.4 1308.44  5226.9 1310.19  5262.1 1310.24  5283.6 1311.61  5326.1 1312.31
  5340.3 1313.18  5361.3 1313.65  5375.5 1314.52  5389.6 1314.52  5396.7 1315.10
#Mann=3,-1,0
  4740.6    0.05       0  4995.7    0.03       0  4999.7    0.05       0
Bank Sta=4995.7,4999.7
Exp/Cntr=0.3,0.1

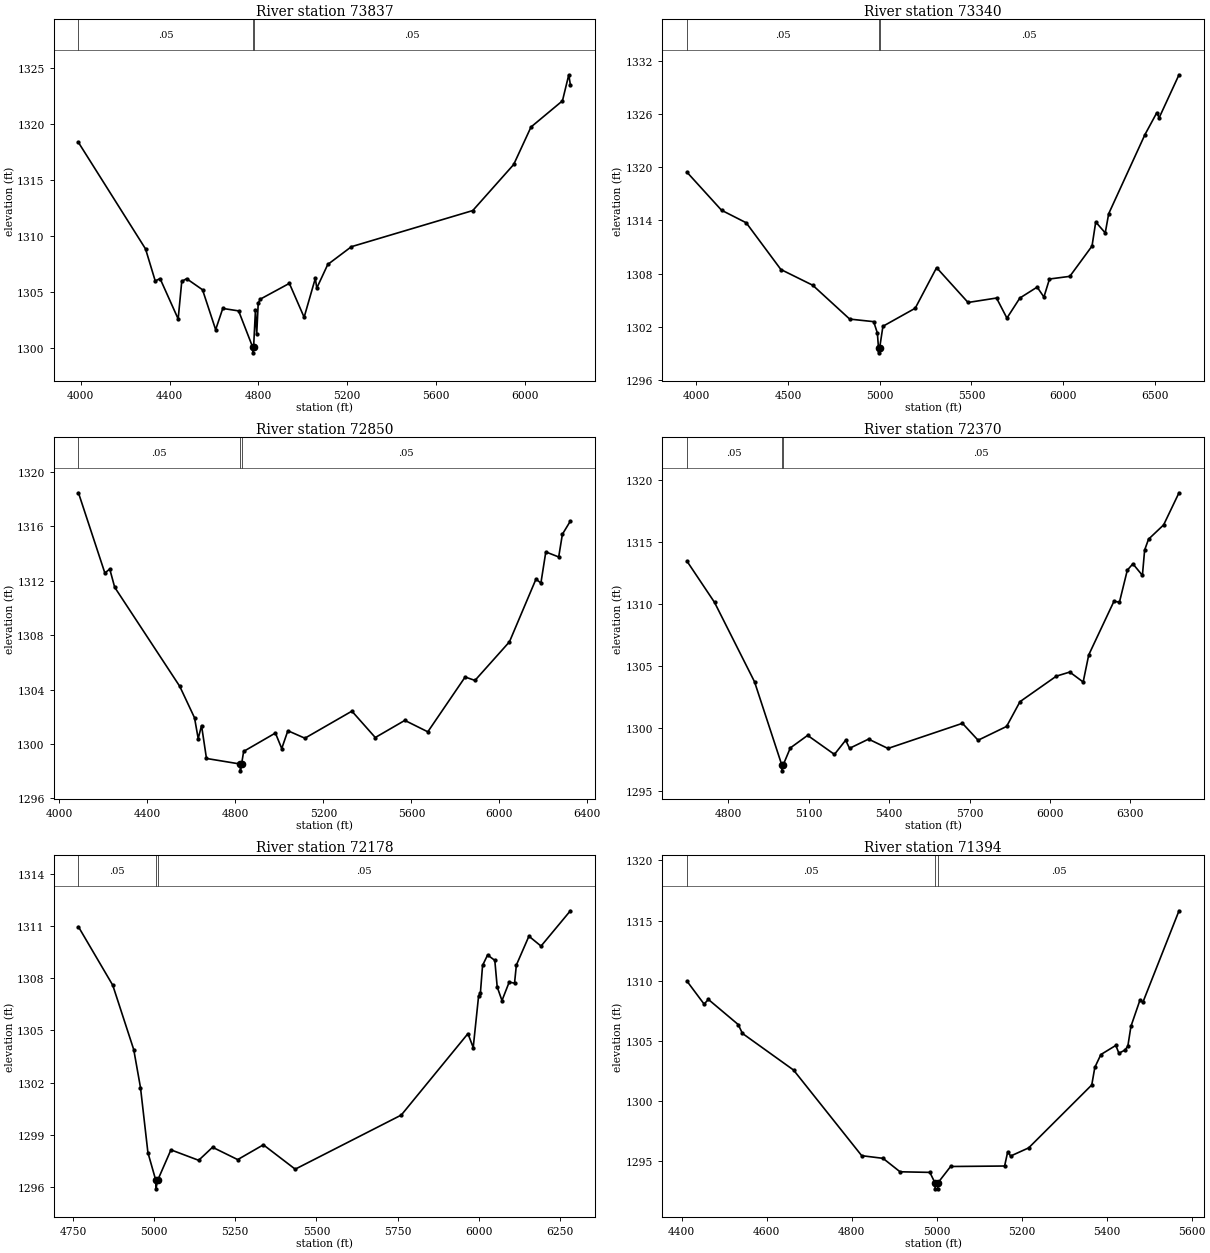
Type RM Length L Ch R = 1,73837,497,497,497
BEGIN DESCRIPTION:
WRIGHTS CREEK 135.0
END DESCRIPTION:
XS GIS Cut Line= 3
      2825255.72     10286153.13      2824369.75     10285668.00
      2823455.65     10286453.14
#Sta/Elev= 30
  3989.9 1318.37  4292.0 1308.85  4335.6 1305.99  4357.4 1306.20  4438.9 1302.59
  4455.1 1305.95  4476.9 1306.19  4548.6 1305.20  4607.7 1301.63  4639.8 1303.53
  4711.1 1303.31  4774.6 1300.06  4774.9 1299.56  4778.6 1300.06  4786.9 1303.38
  4792.6 1301.25  4799.4 1304.00  4808.7 1304.36  4939.6 1305.77  5006.1 1302.74
  5056.5 1306.22  5063.1 1305.35  5112.5 1307.46  5219.0 1309.05  5765.4 1312.28
  5949.8 1316.40  6027.7 1319.75  6169.3 1322.09  6197.8 1324.42  6205.0 1323.51
#Mann=3,-1,0
  3989.9    0.05       0  4774.6    0.05       0  4778.6    0.05       0
Bank Sta=4774.6,4778.6
Exp/Cntr=0.3,0.1

Type RM Length L Ch R = 1,73340,490,490,490
BEGIN DESCRIPTION:
WRIGHTS CREEK 134.0
END DESCRIPTION:
XS GIS Cut Line= 3
      2825665.85     10285561.46      2824622.75     10285432.00
      2823005.70     10285653.11
#Sta/Elev= 30
  3948.9 1319.42  4137.0 1315.15  4271.5 1313.74  4460.6 1308.48  4634.3 1306.71
  4835.8 1302.90  4966.8 1302.61  4987.0 1301.32  4993.1 1299.60  4993.6 1299.10
  4998.9 1299.60  5017.2 1302.09  5193.3 1304.12  5309.9 1308.69  5481.5 1304.77
  5636.8 1305.27  5693.5 1303.01  5764.1 1305.27  5858.5 1306.50  5895.3 1305.38
  5925.6 1307.41  6036.6 1307.71  6157.7 1311.12  6177.9 1313.83  6229.8 1312.60
  6248.6 1314.76  6446.5 1323.67  6511.0 1326.13  6523.8 1325.56  6632.1 1330.40
#Mann=3,-1,0
  3948.9    0.05       0  4993.1    0.05       0  4998.9    0.05       0
Bank Sta=4993.1,4998.9
Exp/Cntr=0.3,0.1

Type RM Length L Ch R = 1,72850,480,480,480
BEGIN DESCRIPTION:
WRIGHTS CREEK 133.0
END DESCRIPTION:
XS GIS Cut Line= 3
      2825355.66     10284553.12      2824539.50     10284963.00
      2823355.72     10285553.09
#Sta/Elev= 30
  4086.7 1318.48  4206.7 1312.58  4229.0 1312.87  4251.4 1311.53  4547.3 1304.24
  4614.3 1301.93  4631.0 1300.40  4646.2 1301.36  4668.6 1298.94  4822.3 1298.53
  4822.8 1298.03  4828.2 1298.53  4837.6 1299.46  4981.9 1300.81  5010.7 1299.67
  5038.6 1300.98  5116.0 1300.43  5329.6 1302.42  5435.9 1300.48  5570.2 1301.74
  5674.7 1300.90  5844.3 1304.93  5889.1 1304.68  6045.8 1307.52  6166.3 1312.13
  6188.7 1311.84  6211.0 1314.13  6269.6 1313.76  6286.4 1315.43  6322.7 1316.40
#Mann=3,-1,0
  4086.7    0.05       0  4822.3    0.03       0  4828.2    0.05       0
Bank Sta=4822.3,4828.2
Exp/Cntr=0.3,0.1

Type RM Length L Ch R = 1,72370,192,192,192
BEGIN DESCRIPTION:
WRIGHTS CREEK 132.0
END DESCRIPTION:
XS GIS Cut Line= 3
      2824655.70     10284253.07      2824492.75     10284567.00
      2823305.70     10285453.10
#Sta/Elev= 30
  4646.3 1313.43  4748.7 1310.13  4897.9 1303.75  4999.2 1297.09  4999.7 1296.59
  5005.3 1297.09  5031.4 1298.43  5096.0 1299.44  5196.0 1297.91  5237.8 1299.05
  5252.4 1298.40  5323.3 1299.14  5395.7 1298.39  5673.5 1300.41  5731.9 1299.05
  5838.2 1300.16  5888.2 1302.15  6023.7 1304.20  6073.8 1304.53  6123.8 1303.73
  6144.6 1305.91  6238.5 1310.21  6259.3 1310.16  6288.5 1312.72  6309.3 1313.23
  6344.8 1312.30  6353.1 1314.34  6367.7 1315.21  6424.0 1316.36  6481.3 1318.94
#Mann=3,-1,0
  4646.3    0.05       0  4999.2    0.05       0  5005.3    0.05       0
Bank Sta=4999.2,5005.3
Exp/Cntr=0.3,0.1

Type RM Length L Ch R = 1,72178,784,784,784
BEGIN DESCRIPTION:
Mapping XS 3f12e5bd
END DESCRIPTION:
XS GIS Cut Line= 3
      2824472.28     10284281.12      2824244.44     10284584.90
      2823235.35     10285105.72
#Sta/Elev= 30
  4766.9 1310.95  4872.6 1307.59  4937.2 1303.89  4958.0 1301.71  4980.9 1297.97
  5005.0 1296.39  5005.5 1295.89  5011.1 1296.39  5051.8 1298.13  5137.2 1297.53
  5180.0 1298.28  5257.4 1297.57  5336.5 1298.42  5434.6 1297.02  5761.3 1300.13
  5966.7 1304.81  5982.9 1304.01  5999.4 1306.96  6005.0 1307.14  6011.7 1308.73
  6027.2 1309.33  6049.4 1309.02  6056.8 1307.49  6071.5 1306.71  6093.7 1307.77
  6110.2 1307.71  6115.8 1308.75  6154.5 1310.41  6191.8 1309.84  6282.2 1311.87
#Mann=3,-1,0
  4766.9    0.05       0  5005.0    0.05       0  5011.1    0.05       0
Bank Sta=5005,5011.1
Exp/Cntr=0.3,0.1

Type RM Length L Ch R = 1,71394,437,437,437
BEGIN DESCRIPTION:
WRIGHTS CREEK 130.0
END DESCRIPTION:
XS GIS Cut Line= 3
      2824355.64     10284203.11      2823769.75     10284161.00
      2823355.66     10284553.14
#Sta/Elev= 30
  4412.6 1309.94  4452.7 1308.04  4462.7 1308.43  4532.9 1306.34  4542.9 1305.60
  4663.2 1302.55  4823.6 1295.42  4873.7 1295.20  4913.8 1294.08  4984.0 1294.03
  4996.0 1293.16  4996.5 1292.66  5002.5 1292.66  5003.0 1293.16  5032.8 1294.52
  5159.9 1294.56  5167.2 1295.75  5174.0 1295.39  5216.5 1296.07  5365.0 1301.31
  5372.2 1302.77  5386.4 1303.84  5421.6 1304.60  5428.9 1303.95  5443.0 1304.21
  5449.9 1304.54  5457.2 1306.19  5478.2 1308.35  5485.5 1308.21  5570.3 1315.81
#Mann=3,-1,0
  4412.6    0.05       0  4996.0    0.03       0  5003.0    0.05       0
Bank Sta=4996,5003
Exp/Cntr=0.3,0.1

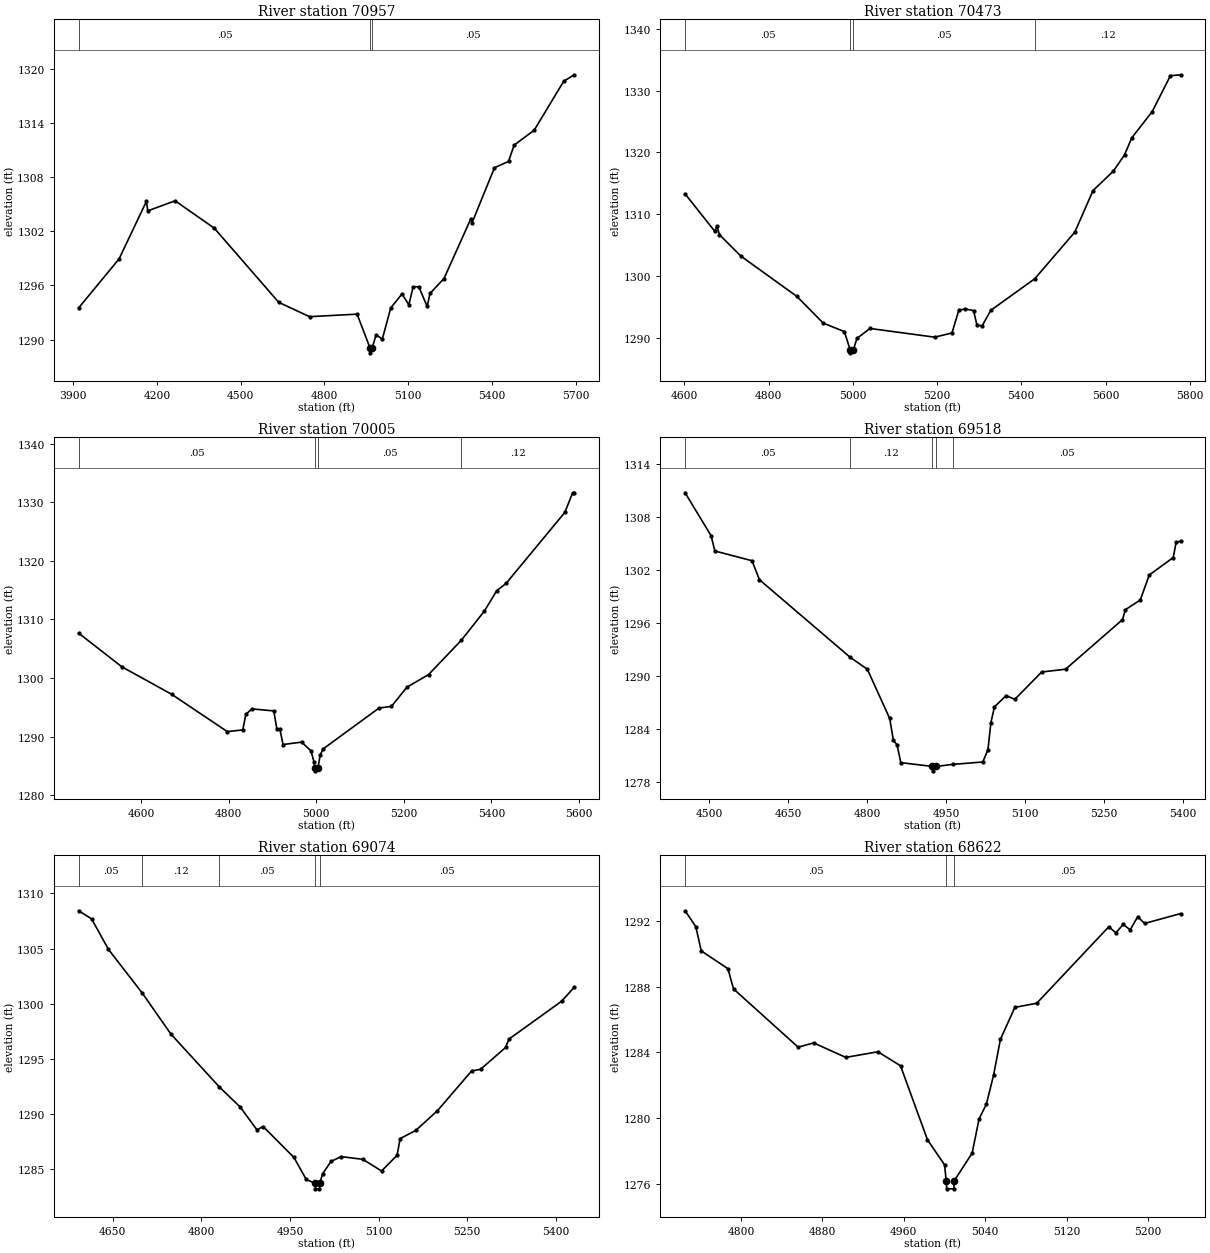
Type RM Length L Ch R = 1,70957,484,484,484
BEGIN DESCRIPTION:
WRIGHTS CREEK 129.0
END DESCRIPTION:
XS GIS Cut Line= 3
      2824700.18     10283760.25      2823622.75     10283839.00
      2822931.55     10283901.31
#Sta/Elev= 30
  3919.7 1293.51  4064.6 1298.95  4162.3 1305.32  4167.3 1304.27  4265.1 1305.39
  4405.5 1302.35  4636.1 1294.13  4746.4 1292.54  4916.8 1292.82  4963.5 1289.03
  4964.0 1288.53  4970.5 1289.03  4984.9 1290.53  5007.1 1290.06  5037.2 1293.51
  5077.4 1295.06  5102.0 1293.86  5117.5 1295.85  5137.6 1295.86  5167.7 1293.67
  5177.8 1295.12  5228.0 1296.77  5323.8 1303.38  5328.8 1302.98  5408.7 1309.06
  5458.9 1309.75  5479.0 1311.56  5550.7 1313.21  5656.6 1318.64  5694.0 1319.36
#Mann=3,-1,0
  3919.7    0.05       0  4963.5    0.05       0  4970.5    0.05       0
Bank Sta=4963.5,4970.5
Exp/Cntr=0.3,0.1

Type RM Length L Ch R = 1,70473,468,468,468
BEGIN DESCRIPTION:
WRIGHTS CREEK 128.0
END DESCRIPTION:
XS GIS Cut Line= 3
      2824155.66     10283353.12      2823765.25     10283433.00
      2823005.67     10283603.12
#Sta/Elev= 30
  4601.5 1313.28  4672.1 1307.21  4677.2 1308.06  4683.1 1306.67  4734.2 1303.19
  4866.9 1296.67  4929.5 1292.34  4979.9 1290.96  4993.4 1288.02  4993.9 1287.52
  5001.1 1288.02  5009.8 1289.87  5040.5 1291.47  5194.3 1290.06  5235.3 1290.74
  5251.4 1294.39  5266.0 1294.65  5286.5 1294.36  5294.8 1291.99  5307.0 1291.90
  5327.5 1294.41  5431.8 1299.52  5527.0 1307.08  5570.4 1313.83  5618.9 1316.99
  5645.2 1319.62  5662.3 1322.37  5710.8 1326.61  5754.1 1332.44  5778.4 1332.59
#Mann=4,-1,0
  4601.5    0.05       0  4993.4    0.03       0  5001.1    0.05       0
  5431.8    0.12       0
Bank Sta=4993.4,5001.1
Exp/Cntr=0.3,0.1

Type RM Length L Ch R = 1,70005,487,487,487
BEGIN DESCRIPTION:
WRIGHTS CREEK 127.0
END DESCRIPTION:
XS GIS Cut Line= 3
      2823805.70     10282753.10      2823423.25     10283138.00
      2823005.68     10283553.12
#Sta/Elev= 30
  4457.4 1307.65  4556.4 1301.89  4669.5 1297.23  4796.8 1290.85  4832.2 1291.13
  4839.2 1293.82  4853.4 1294.72  4902.9 1294.38  4910.0 1291.32  4917.0 1291.22
  4924.1 1288.64  4966.5 1289.05  4987.8 1287.57  4994.7 1285.71  4996.1 1284.65
  4996.6 1284.15  5003.9 1284.65  5009.0 1286.90  5016.0 1287.91  5143.3 1294.87
  5171.6 1295.15  5207.0 1298.43  5256.4 1300.58  5331.3 1306.45  5383.7 1311.41
  5412.0 1314.90  5433.2 1316.13  5567.6 1328.27  5585.3 1331.61  5588.8 1331.61
#Mann=4,-1,0
  4457.4    0.05       0  4996.1    0.03       0  5003.9    0.05       0
  5331.3    0.12       0
Bank Sta=4996.1,5003.9
Exp/Cntr=0.3,0.1

Type RM Length L Ch R = 1,69518,444,444,444
BEGIN DESCRIPTION:
WRIGHTS CREEK 126.0
END DESCRIPTION:
XS GIS Cut Line= 3
      2823605.70     10282303.09      2823225.25     10282695.00
      2823055.70     10283053.09
#Sta/Elev= 30
  4453.8 1310.71  4503.3 1305.85  4510.3 1304.13  4581.0 1303.03  4595.2 1300.88
  4767.8 1292.11  4800.4 1290.76  4842.9 1285.20  4849.8 1282.76  4857.0 1282.20
  4864.0 1280.21  4923.8 1279.78  4924.3 1279.28  4931.6 1279.78  4962.6 1280.01
  5020.0 1280.28  5029.8 1281.68  5035.3 1284.72  5042.2 1286.52  5064.3 1287.79
  5080.8 1287.36  5131.9 1290.45  5177.4 1290.77  5285.6 1296.37  5291.1 1297.49
  5319.4 1298.59  5336.6 1301.42  5382.1 1303.39  5387.6 1305.10  5396.2 1305.24
#Mann=5,-1,0
  4453.8    0.05       0  4767.8    0.12       0  4923.8    0.03       0
  4931.6    0.12       0  4962.6    0.05       0
Bank Sta=4923.8,4931.6
Exp/Cntr=0.3,0.1

Type RM Length L Ch R = 1,69074,452,452,452
BEGIN DESCRIPTION:
WRIGHTS CREEK 125.0
END DESCRIPTION:
XS GIS Cut Line= 3
      2823505.70     10282153.11      2823114.25     10282266.00
      2822705.65     10282403.12
#Sta/Elev= 30
  4592.6 1308.43  4614.6 1307.69  4643.1 1304.92  4700.6 1300.93  4748.7 1297.23
  4830.8 1292.42  4865.8 1290.61  4894.3 1288.53  4904.8 1288.83  4956.9 1286.02
  4977.7 1284.02  4992.7 1283.67  4993.2 1283.17  5000.1 1283.17  5000.6 1283.67
  5005.2 1284.52  5019.6 1285.66  5036.7 1286.10  5073.5 1285.85  5105.1 1284.79
  5131.4 1286.22  5136.6 1287.74  5162.9 1288.47  5199.7 1290.27  5257.5 1293.88
  5272.7 1294.03  5314.9 1296.01  5320.6 1296.77  5409.9 1300.22  5431.0 1301.48
#Mann=5,-1,0
  4592.6    0.05       0  4700.6    0.12       0  4830.8    0.05       0
  4992.7    0.03       0  5000.6    0.05       0
Bank Sta=4992.7,5000.6
Exp/Cntr=0.3,0.1

Type RM Length L Ch R = 1,68622,493,493,493
BEGIN DESCRIPTION:
WRIGHTS CREEK 124.0
END DESCRIPTION:
XS GIS Cut Line= 3
      2823155.66     10281853.12      2822913.50     10281933.00
      2822755.71     10282103.08
#Sta/Elev= 30
  4745.0 1292.61  4755.5 1291.65  4760.9 1290.17  4787.1 1289.09  4792.6 1287.86
  4856.1 1284.32  4871.3 1284.58  4902.9 1283.70  4934.5 1284.04  4956.7 1283.19
  4983.2 1278.69  5000.0 1277.17  5001.6 1276.21  5002.1 1275.71  5009.1 1275.71
  5009.6 1276.21  5027.1 1277.88  5033.9 1279.96  5041.1 1280.86  5048.1 1282.60
  5054.9 1284.80  5069.1 1286.74  5090.6 1286.99  5161.4 1291.64  5168.3 1291.27
  5175.6 1291.78  5182.4 1291.45  5189.8 1292.25  5196.6 1291.84  5232.0 1292.44
#Mann=3,-1,0
  4745.0    0.05       0  5001.6    0.05       0  5009.6    0.05       0
Bank Sta=5001.6,5009.6
Exp/Cntr=0.3,0.1