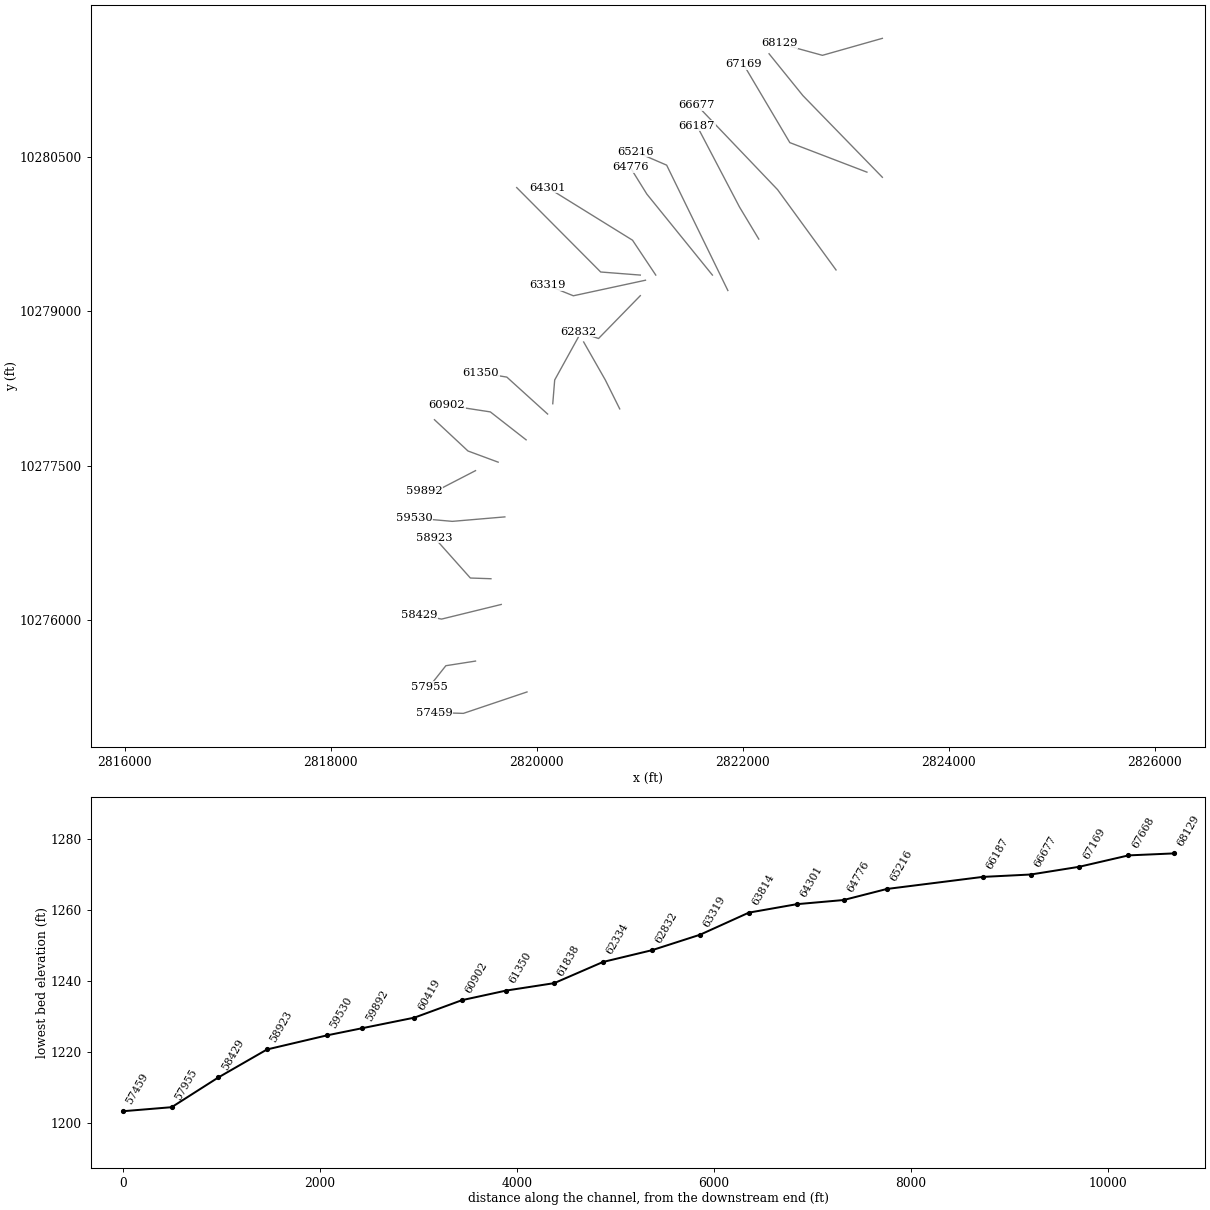
HEC-RAS study WRIGHTS CREEK.prj: WRIGHTS CREEK Base Level Engineering

--- WRIGHTS CREEK.g01 (geometry) --- (continued)

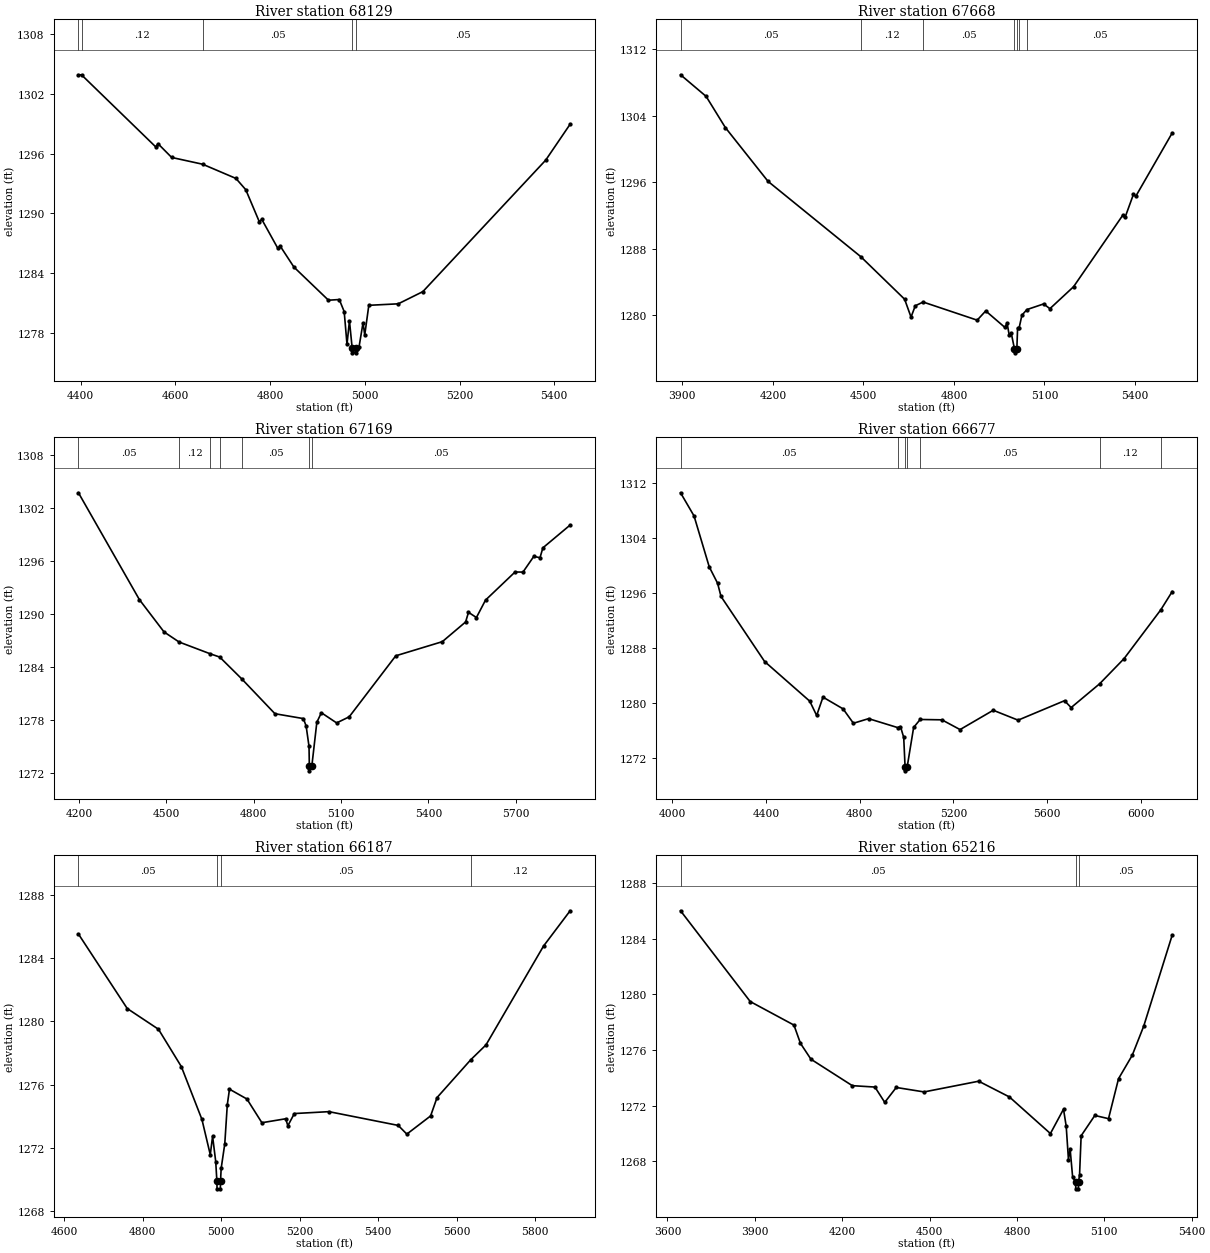
Type RM Length L Ch R = 1,68129,461,461,461
BEGIN DESCRIPTION:
WRIGHTS CREEK 123.0
END DESCRIPTION:
XS GIS Cut Line= 3
      2823355.68     10281653.11      2822773.75     10281488.00
      2822355.71     10281603.11
#Sta/Elev= 30
  4395.1 1303.89  4401.7 1303.88  4558.1 1296.68  4563.3 1296.98  4592.0 1295.61
  4657.5 1294.93  4727.7 1293.51  4748.5 1292.38  4777.1 1289.17  4782.3 1289.41
  4816.2 1286.51  4821.4 1286.72  4850.2 1284.63  4923.2 1281.31  4946.0 1281.38
  4956.4 1280.17  4962.3 1276.90  4967.5 1279.24  4973.2 1276.54  4973.7 1276.04
  4980.8 1276.04  4981.3 1276.54  4987.6 1276.59  4996.2 1279.05  4999.8 1277.83
  5008.4 1280.80  5070.6 1280.95  5122.5 1282.17  5382.0 1295.34  5433.6 1298.94
#Mann=5,-1,0
  4395.1    0.05       0  4401.7    0.12       0  4657.5    0.05       0
  4973.2    0.05       0  4981.3    0.05       0
Bank Sta=4973.2,4981.3
Exp/Cntr=0.3,0.1

Type RM Length L Ch R = 1,67668,499,499,499
BEGIN DESCRIPTION:
WRIGHTS CREEK 122.0
END DESCRIPTION:
XS GIS Cut Line= 3
      2823355.69     10280303.11      2822584.75     10281096.00
      2822255.67     10281503.13
#Sta/Elev= 30
  3894.1 1308.92  3978.9 1306.32  4042.6 1302.57  4184.1 1296.10  4491.2 1287.05
  4636.6 1281.93  4657.9 1279.78  4672.0 1281.14  4698.0 1281.59  4877.1 1279.41
  4905.4 1280.52  4968.9 1278.54  4976.1 1279.08  4983.1 1277.64  4990.2 1277.82
  5000.5 1275.98  5001.0 1275.48  5008.6 1275.98  5011.0 1278.44  5016.0 1278.47
  5025.4 1280.01  5041.8 1280.68  5097.3 1281.36  5118.1 1280.79  5196.5 1283.43
  5359.6 1292.03  5367.5 1291.80  5394.9 1294.54  5402.7 1294.31  5523.5 1301.93
#Mann=7,-1,0
  3894.1    0.05       0  4491.2    0.12       0  4698.0    0.05       0
  5000.5    0.03       0  5008.6    0.05       0  5016.0    0.12       0
  5041.8    0.05       0
Bank Sta=5000.5,5008.6
Exp/Cntr=0.3,0.1

Type RM Length L Ch R = 1,67169,492,492,492
BEGIN DESCRIPTION:
WRIGHTS CREEK 121.0
END DESCRIPTION:
XS GIS Cut Line= 3
      2823205.65     10280353.12      2822457.25     10280640.00
      2822005.69     10281403.10
#Sta/Elev= 30
  4198.5 1303.73  4407.7 1291.65  4492.4 1287.99  4544.1 1286.85  4651.6 1285.51
  4683.5 1285.15  4759.2 1282.68  4873.2 1278.74  4970.8 1278.19  4980.3 1277.35
  4990.2 1275.04  4991.3 1272.78  4991.8 1272.28  4999.7 1272.78  5017.0 1277.77
  5032.6 1278.85  5085.0 1277.70  5128.2 1278.39  5288.0 1285.29  5447.9 1286.89
  5527.9 1289.12  5537.7 1290.21  5564.9 1289.62  5596.2 1291.59  5697.6 1294.77
  5724.8 1294.76  5761.9 1296.53  5783.3 1296.39  5793.1 1297.50  5886.7 1300.08
#Mann=7,-1,0
  4198.5    0.05       0  4544.1    0.12       0  4651.6    0.05       0
  4683.5    0.12       0  4759.2    0.05       0  4991.3    0.05       0
  4999.7    0.05       0
Bank Sta=4991.3,4999.7
Exp/Cntr=0.3,0.1

Type RM Length L Ch R = 1,66677,490,490,490
BEGIN DESCRIPTION:
WRIGHTS CREEK 120.0
END DESCRIPTION:
XS GIS Cut Line= 3
      2822905.70     10279403.09      2822338.25     10280183.00
      2821555.67     10281003.13
#Sta/Elev= 30
  4035.5 1310.54  4093.1 1307.17  4158.0 1299.76  4193.6 1297.38  4208.2 1295.46
  4394.2 1286.00  4586.9 1280.23  4616.3 1278.15  4643.3 1280.82  4729.1 1279.11
  4773.1 1277.02  4838.0 1277.69  4962.1 1276.39  4974.0 1276.54  4987.8 1274.96
  4993.7 1270.60  4994.2 1270.10  5002.2 1270.60  5030.1 1276.41  5058.0 1277.57
  5150.6 1277.52  5228.2 1276.10  5369.8 1278.91  5475.8 1277.47  5673.9 1280.30
  5702.2 1279.30  5824.1 1282.77  5928.3 1286.43  6085.0 1293.53  6133.6 1296.18
#Mann=7,-1,0
  4035.5    0.05       0  4962.1    0.12       0  4993.7    0.07       0
  5002.2    0.12       0  5058.0    0.05       0  5824.1    0.12       0
  6085.0    0.05       0
Bank Sta=4993.7,5002.2
Exp/Cntr=0.3,0.1

Type RM Length L Ch R = 1,66187,971,971,971
BEGIN DESCRIPTION:
WRIGHTS CREEK 119.0
END DESCRIPTION:
XS GIS Cut Line= 3
      2822155.70     10279703.09      2821968.25     10280015.00
      2821555.67     10280803.14
#Sta/Elev= 30
  4636.1 1285.53  4760.5 1280.82  4840.1 1279.51  4898.4 1277.15  4950.9 1273.81
  4972.2 1271.58  4978.1 1272.74  4986.1 1271.14  4989.0 1269.92  4989.5 1269.42
  4997.8 1269.42  4998.3 1269.92  5000.0 1270.72  5009.2 1272.27  5015.6 1274.74
  5021.2 1275.72  5065.6 1275.10  5103.8 1273.60  5164.4 1273.85  5170.0 1273.41
  5186.5 1274.18  5274.7 1274.30  5451.3 1273.43  5473.3 1272.88  5533.9 1274.03
  5550.3 1275.19  5636.2 1277.58  5675.1 1278.52  5821.8 1284.77  5889.6 1287.00
#Mann=4,-1,0
  4636.1    0.05       0  4989.0    0.05       0  4998.3    0.05       0
  5636.2    0.12       0
Bank Sta=4989,4998.3
Exp/Cntr=0.3,0.1

Type RM Length L Ch R = 1,65216,440,440,440
BEGIN DESCRIPTION:
WRIGHTS CREEK 118.0
END DESCRIPTION:
XS GIS Cut Line= 3
      2821855.68     10279203.12      2821261.50     10280421.00
      2820955.71     10280553.10
#Sta/Elev= 30
  3644.9 1286.00  3884.2 1279.48  4034.3 1277.79  4056.6 1276.48  4092.6 1275.34
  4234.6 1273.44  4312.3 1273.34  4346.0 1272.24  4385.5 1273.31  4481.1 1272.99
  4668.5 1273.76  4774.0 1272.63  4914.8 1270.00  4959.8 1271.75  4969.0 1270.53
  4976.8 1268.12  4982.4 1268.91  4991.2 1266.86  5001.3 1266.53  5001.8 1266.03
  5010.8 1266.03  5011.3 1266.53  5014.9 1267.04  5020.3 1269.84  5067.3 1271.30
  5114.3 1271.07  5148.7 1273.94  5195.7 1275.62  5235.1 1277.71  5333.1 1284.26
#Mann=3,-1,0
  3644.9    0.05       0  5001.3    0.03       0  5011.3    0.05       0
Bank Sta=5001.3,5011.3
Exp/Cntr=0.3,0.1

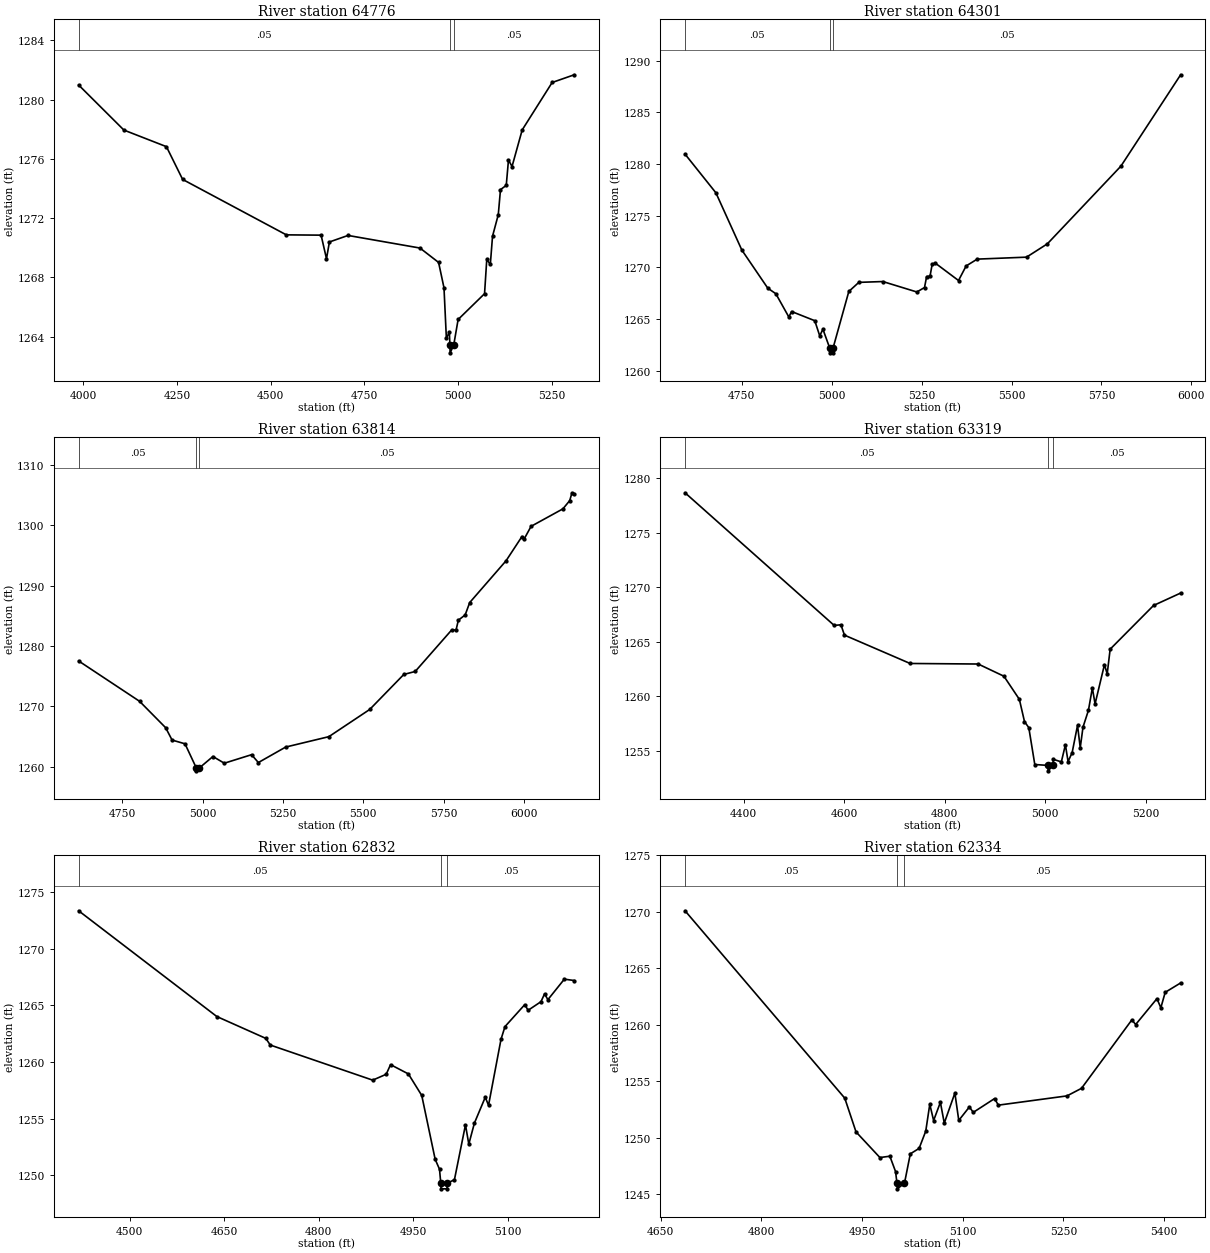
Type RM Length L Ch R = 1,64776,475,475,475
BEGIN DESCRIPTION:
WRIGHTS CREEK 117.0
END DESCRIPTION:
XS GIS Cut Line= 3
      2821705.68     10279353.12      2821069.00     10280140.00
      2820905.67     10280403.13
#Sta/Elev= 30
  3987.8 1280.98  4108.5 1277.94  4222.0 1276.82  4265.2 1274.61  4541.8 1270.87
  4634.5 1270.85  4648.9 1269.26  4656.7 1270.39  4706.4 1270.83  4898.3 1269.98
  4947.9 1269.01  4962.3 1267.30  4968.7 1263.88  4976.6 1264.32  4978.1 1263.41
  4978.6 1262.91  4988.1 1263.41  5000.0 1265.16  5070.5 1266.90  5076.4 1269.21
  5085.9 1268.88  5091.8 1270.78  5107.1 1272.23  5113.0 1273.92  5128.4 1274.21
  5134.3 1275.92  5143.8 1275.48  5170.9 1277.95  5250.8 1281.15  5309.7 1281.67
#Mann=3,-1,0
  3987.8    0.05       0  4978.1    0.05       0  4988.1    0.05       0
Bank Sta=4978.1,4988.1
Exp/Cntr=0.3,0.1

Type RM Length L Ch R = 1,64301,487,487,487
BEGIN DESCRIPTION:
WRIGHTS CREEK 116.0
END DESCRIPTION:
XS GIS Cut Line= 3
      2821155.71     10279353.08      2820930.00     10279692.00
      2820105.70     10280203.10
#Sta/Elev= 30
  4592.8 1280.97  4678.5 1277.23  4750.6 1271.69  4822.7 1268.00  4845.1 1267.46
  4881.2 1265.21  4888.9 1265.74  4953.3 1264.85  4967.0 1263.39  4976.0 1264.02
  4994.4 1262.24  4994.9 1261.74  5003.9 1261.74  5004.4 1262.24  5047.9 1267.68
  5075.7 1268.56  5142.4 1268.64  5236.9 1267.63  5258.2 1268.06  5264.1 1269.12
  5273.5 1269.15  5279.4 1270.29  5287.5 1270.44  5352.7 1268.74  5373.9 1270.15
  5404.7 1270.81  5541.7 1271.00  5599.6 1272.29  5804.0 1279.81  5969.9 1288.65
#Mann=3,-1,0
  4592.8    0.05       0  4994.4    0.03       0  5004.4    0.05       0
Bank Sta=4994.4,5004.4
Exp/Cntr=0.3,0.1

Type RM Length L Ch R = 1,63814,495,495,495
BEGIN DESCRIPTION:
WRIGHTS CREEK 115.0
END DESCRIPTION:
XS GIS Cut Line= 3
      2821005.64     10279353.11      2820621.00     10279383.00
      2819805.70     10280203.09
#Sta/Elev= 30
  4614.2 1277.53  4803.8 1270.86  4885.0 1266.49  4905.0 1264.45  4945.2 1263.83
  4980.2 1259.86  4980.7 1259.36  4990.3 1259.86  5032.1 1261.73  5067.5 1260.62
  5152.3 1262.03  5173.5 1260.73  5258.4 1263.29  5392.8 1265.01  5520.0 1269.51
  5626.1 1275.30  5661.5 1275.79  5774.6 1282.63  5788.7 1282.66  5795.8 1284.27
  5817.0 1285.14  5831.2 1287.19  5944.3 1294.10  5993.8 1298.11  6000.9 1297.73
  6022.1 1299.79  6121.1 1302.68  6142.3 1304.04  6149.4 1305.34  6156.4 1305.07
#Mann=3,-1,0
  4614.2    0.05       0  4980.2    0.05       0  4990.3    0.05       0
Bank Sta=4980.2,4990.3
Exp/Cntr=0.3,0.1

Type RM Length L Ch R = 1,63319,487,487,487
BEGIN DESCRIPTION:
WRIGHTS CREEK 114.0
END DESCRIPTION:
XS GIS Cut Line= 3
      2821055.68     10279303.11      2820355.50     10279152.00
      2820105.69     10279253.11
#Sta/Elev= 30
  4283.7 1278.65  4580.4 1266.48  4593.8 1266.54  4600.8 1265.59  4731.4 1262.99
  4866.8 1262.94  4918.0 1261.82  4948.7 1259.70  4958.9 1257.66  4967.5 1257.10
  4979.4 1253.72  5005.4 1253.64  5005.9 1253.14  5015.8 1253.64  5016.1 1254.20
  5032.2 1253.96  5040.3 1255.53  5045.6 1253.99  5053.7 1254.81  5064.4 1257.31
  5069.8 1255.26  5075.3 1257.15  5086.1 1258.69  5093.9 1260.74  5099.3 1259.28
  5118.0 1262.89  5123.4 1262.03  5129.3 1264.30  5215.6 1268.31  5269.5 1269.45
#Mann=3,-1,0
  4283.7    0.05       0  5005.4    0.05       0  5015.8    0.05       0
Bank Sta=5005.4,5015.8
Exp/Cntr=0.3,0.1

Type RM Length L Ch R = 1,62832,498,498,498
BEGIN DESCRIPTION:
WRIGHTS CREEK 113.0
END DESCRIPTION:
XS GIS Cut Line= 3
      2821005.71     10279153.13      2820600.25     10278737.00
      2820405.68     10278803.11
#Sta/Elev= 30
  4419.0 1273.35  4638.3 1264.01  4716.0 1262.08  4723.2 1261.49  4885.7 1258.39
  4907.1 1258.91  4914.0 1259.76  4942.3 1258.94  4963.5 1257.04  4984.8 1251.40
  4991.7 1250.52  4993.7 1249.29  4994.2 1248.79  5003.6 1248.79  5004.1 1249.29
  5015.4 1249.60  5032.9 1254.44  5038.2 1252.74  5047.1 1254.60  5064.3 1256.88
  5069.5 1256.17  5089.3 1262.00  5095.6 1263.12  5127.0 1265.06  5132.3 1264.56
  5152.7 1265.32  5158.4 1266.01  5163.7 1265.50  5189.8 1267.31  5205.5 1267.19
#Mann=3,-1,0
  4419.0    0.05       0  4993.7    0.05       0  5004.1    0.05       0
Bank Sta=4993.7,5004.1
Exp/Cntr=0.3,0.1

Type RM Length L Ch R = 1,62334,496,496,496
BEGIN DESCRIPTION:
WRIGHTS CREEK 112.0
END DESCRIPTION:
XS GIS Cut Line= 3
      2820805.68     10278053.11      2820666.00     10278334.00
      2820455.70     10278703.09
#Sta/Elev= 30
  4686.3 1270.09  4924.3 1253.50  4941.1 1250.51  4976.7 1248.24  4991.5 1248.36
  5000.0 1247.00  5002.1 1245.97  5002.6 1245.47  5013.3 1245.97  5022.0 1248.57
  5035.1 1249.05  5045.0 1250.58  5051.0 1252.96  5056.7 1251.52  5066.8 1253.13
  5072.6 1251.29  5088.4 1253.95  5094.2 1251.53  5110.0 1252.72  5115.8 1252.24
  5147.5 1253.46  5153.2 1252.88  5255.5 1253.70  5277.1 1254.37  5352.1 1260.43
  5357.8 1260.02  5389.5 1262.31  5395.3 1261.50  5401.8 1262.87  5424.8 1263.70
#Mann=3,-1,0
  4686.3    0.05       0  5002.1    0.05       0  5013.3    0.05       0
Bank Sta=5002.1,5013.3
Exp/Cntr=0.3,0.1

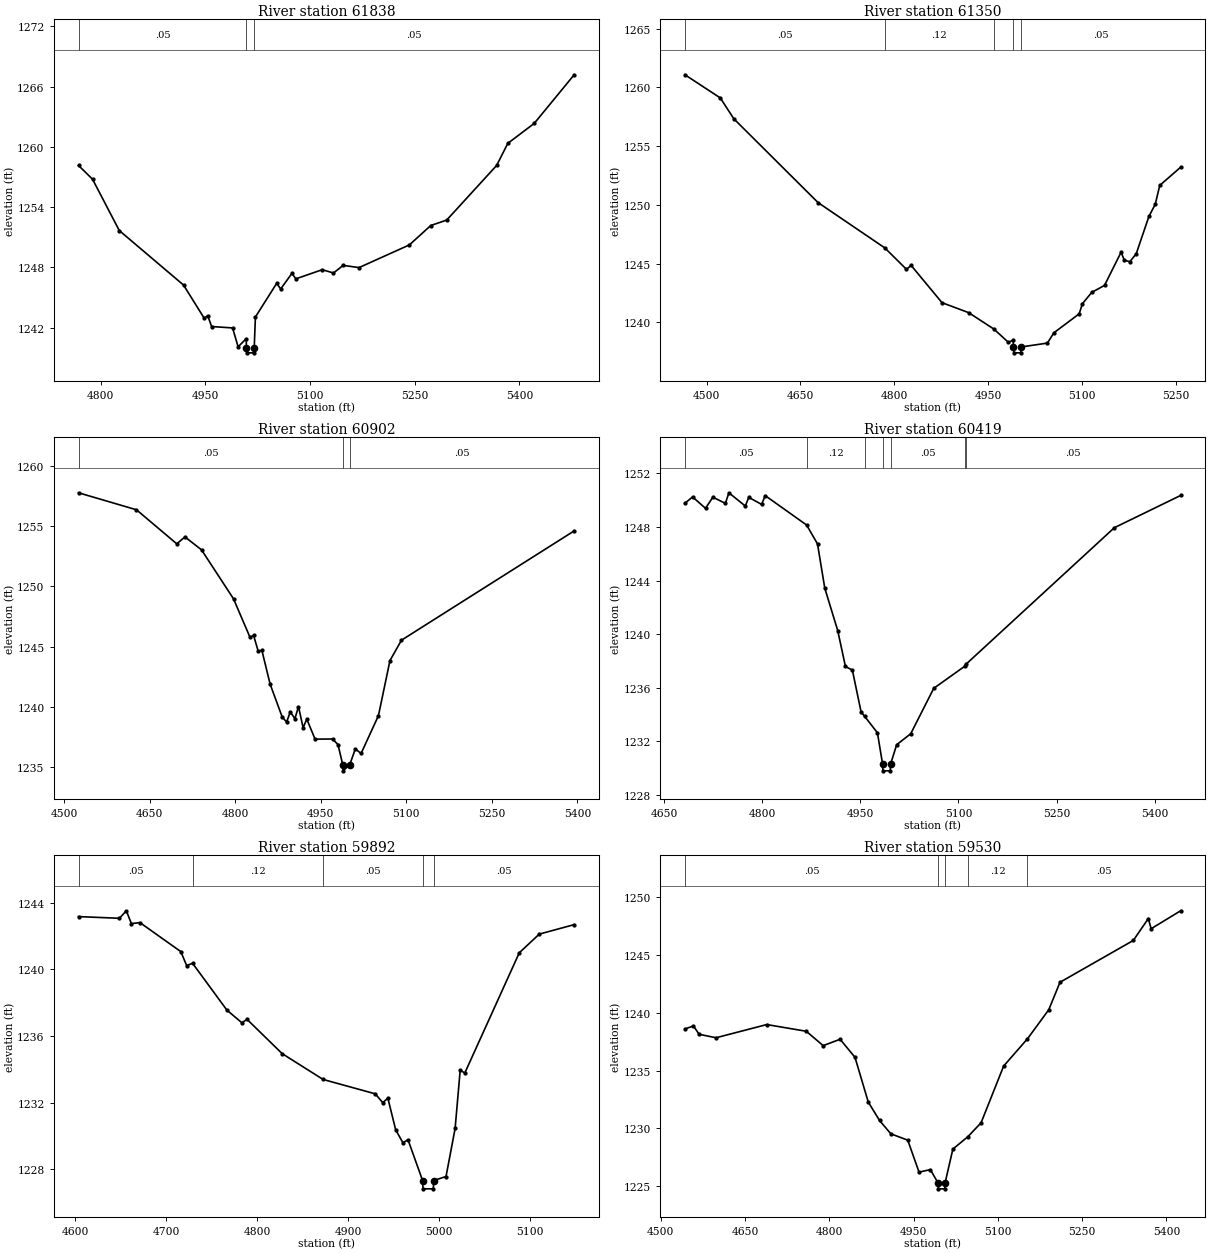
Type RM Length L Ch R = 1,61838,488,488,488
BEGIN DESCRIPTION:
WRIGHTS CREEK 111.0
END DESCRIPTION:
XS GIS Cut Line= 3
      2820155.68     10278103.07      2820174.50     10278334.00
      2820405.66     10278753.07
#Sta/Elev= 30
  4768.3 1258.16  4788.4 1256.79  4826.7 1251.68  4918.8 1246.25  4948.5 1242.94
  4953.5 1243.20  4959.0 1242.12  4989.1 1241.98  4997.0 1240.10  5008.7 1240.91
  5008.9 1240.00  5009.4 1239.50  5019.6 1239.50  5020.1 1240.00  5021.8 1243.07
  5052.3 1246.42  5058.0 1245.86  5074.1 1247.41  5079.8 1246.87  5117.6 1247.78
  5133.7 1247.45  5147.5 1248.21  5170.3 1247.99  5242.5 1250.25  5273.1 1252.18
  5295.9 1252.72  5367.5 1258.16  5383.5 1260.36  5421.4 1262.35  5478.6 1267.19
#Mann=3,-1,0
  4768.3    0.05       0  5008.9    0.05       0  5020.1    0.05       0
Bank Sta=5008.9,5020.1
Exp/Cntr=0.3,0.1

Type RM Length L Ch R = 1,61350,448,448,448
BEGIN DESCRIPTION:
WRIGHTS CREEK 110.0
END DESCRIPTION:
XS GIS Cut Line= 3
      2820105.70     10278003.10      2819709.75     10278362.00
      2819455.66     10278403.12
#Sta/Elev= 30
  4465.6 1261.08  4522.0 1259.11  4543.7 1257.33  4678.2 1250.20  4784.9 1246.34
  4819.4 1244.52  4826.9 1244.85  4876.2 1241.68  4918.8 1240.83  4959.2 1239.43
  4982.3 1238.30  4989.7 1238.49  4990.4 1237.91  4990.9 1237.41  5002.1 1237.41
  5002.6 1237.91  5044.6 1238.24  5054.8 1239.11  5095.3 1240.73  5100.6 1241.60
  5115.5 1242.56  5135.8 1243.15  5162.3 1245.98  5167.4 1245.29  5176.3 1245.17
  5186.5 1245.85  5206.7 1249.02  5216.9 1250.06  5224.0 1251.66  5257.4 1253.21
#Mann=5,-1,0
  4465.6    0.05       0  4784.9    0.12       0  4959.2    0.05       0
  4990.4    0.03       0  5002.6    0.05       0
Bank Sta=4990.4,5002.6
Exp/Cntr=0.3,0.1

Type RM Length L Ch R = 1,60902,483,483,483
BEGIN DESCRIPTION:
Mapping XS cf77a11a
END DESCRIPTION:
XS GIS Cut Line= 3
      2819896.95     10277752.57      2819549.71     10278023.85
      2819126.53     10278088.96
#Sta/Elev= 30
  4525.4 1257.76  4627.0 1256.35  4697.6 1253.53  4712.0 1254.10  4741.0 1253.03
  4797.1 1248.97  4826.0 1245.78  4832.3 1245.93  4840.5 1244.61  4846.8 1244.70
  4861.3 1241.89  4882.3 1239.19  4890.2 1238.75  4896.6 1239.60  4904.7 1239.03
  4911.0 1240.04  4919.1 1238.28  4925.5 1239.00  4940.0 1237.34  4970.6 1237.35
  4980.2 1236.89  4988.6 1235.21  4989.1 1234.71  5000.8 1235.21  5010.6 1236.53
  5020.7 1236.15  5051.1 1239.28  5071.3 1243.85  5091.5 1245.54  5394.2 1254.60
#Mann=3,-1,0
  4525.4    0.05       0  4988.6    0.05       0  5000.8    0.05       0
Bank Sta=4988.6,5000.8
Exp/Cntr=0.3,0.1

Type RM Length L Ch R = 1,60419,527,527,527
BEGIN DESCRIPTION:
Mapping XS 46d536d4
END DESCRIPTION:
XS GIS Cut Line= 3
      2819625.67     10277535.57      2819332.69     10277644.08
      2819007.17     10277947.90
#Sta/Elev= 30
  4681.9 1249.77  4693.5 1250.24  4713.3 1249.39  4724.5 1250.22  4743.7 1249.76
  4749.0 1250.55  4774.1 1249.56  4779.4 1250.21  4799.1 1249.68  4804.5 1250.34
  4867.9 1248.14  4884.5 1246.73  4895.6 1243.43  4915.4 1240.26  4927.2 1237.58
  4937.8 1237.31  4951.1 1234.19  4956.7 1233.85  4976.1 1232.63  4984.0 1230.29
  4984.5 1229.79  4995.7 1229.79  4996.2 1230.29  5005.5 1231.74  5027.0 1232.56
  5062.2 1235.95  5109.6 1237.60  5111.5 1237.75  5338.2 1247.94  5439.6 1250.35
#Mann=7,-1,0
  4681.9    0.05       0  4867.9    0.12       0  4956.7    0.05       0
  4984.0    0.05       0  4996.2    0.05       0  5109.6    0.12       0
  5111.5    0.05       0
Bank Sta=4984,4996.2
Exp/Cntr=0.3,0.1

Type RM Length L Ch R = 1,59892,362,362,362
BEGIN DESCRIPTION:
WRIGHTS CREEK 107.0
END DESCRIPTION:
XS GIS Cut Line= 3
      2819405.70     10277453.12      2819053.50     10277271.00
      2818905.68     10277253.11
#Sta/Elev= 30
  4603.5 1243.16  4648.5 1243.06  4656.1 1243.51  4661.7 1242.74  4671.1 1242.80
  4716.1 1241.06  4722.5 1240.22  4729.0 1240.36  4766.8 1237.55  4783.3 1236.79
  4788.9 1237.00  4827.6 1234.94  4872.7 1233.39  4930.0 1232.53  4938.3 1232.00
  4943.9 1232.27  4952.5 1230.37  4960.4 1229.60  4966.1 1229.77  4982.1 1227.33
  4982.6 1226.83  4993.9 1226.83  4994.4 1227.33  5007.9 1227.57  5017.9 1230.45
  5023.5 1233.96  5028.5 1233.77  5088.5 1240.99  5110.5 1242.11  5148.9 1242.68
#Mann=5,-1,0
  4603.5    0.05       0  4729.0    0.12       0  4872.7    0.05       0
  4982.1    0.05       0  4994.4    0.05       0
Bank Sta=4982.1,4994.4
Exp/Cntr=0.3,0.1

Type RM Length L Ch R = 1,59530,607,607,607
BEGIN DESCRIPTION:
Mapping XS 3abde78b
END DESCRIPTION:
XS GIS Cut Line= 3
      2819690.78     10277003.89      2819180.79     10276960.48
      2818811.86     10276993.04
#Sta/Elev= 30
  4543.0 1238.59  4558.1 1238.85  4568.2 1238.13  4598.3 1237.83  4688.6 1238.97
  4758.9 1238.39  4789.0 1237.15  4819.1 1237.70  4845.6 1236.14  4869.3 1232.27
  4889.3 1230.69  4909.4 1229.54  4939.5 1228.99  4959.6 1226.23  4979.7 1226.45
  4993.5 1225.29  4994.0 1224.79  5005.4 1224.79  5005.9 1225.29  5019.8 1228.22
  5046.5 1229.29  5070.0 1230.49  5110.2 1235.39  5152.6 1237.74  5190.5 1240.25
  5210.5 1242.62  5341.0 1246.23  5367.7 1248.12  5372.7 1247.24  5425.2 1248.79
#Mann=5,-1,0
  4543.0    0.05       0  4993.5    0.05       0  5005.9    0.05       0
  5046.5    0.12       0  5152.6    0.05       0
Bank Sta=4993.5,5005.9
Exp/Cntr=0.3,0.1

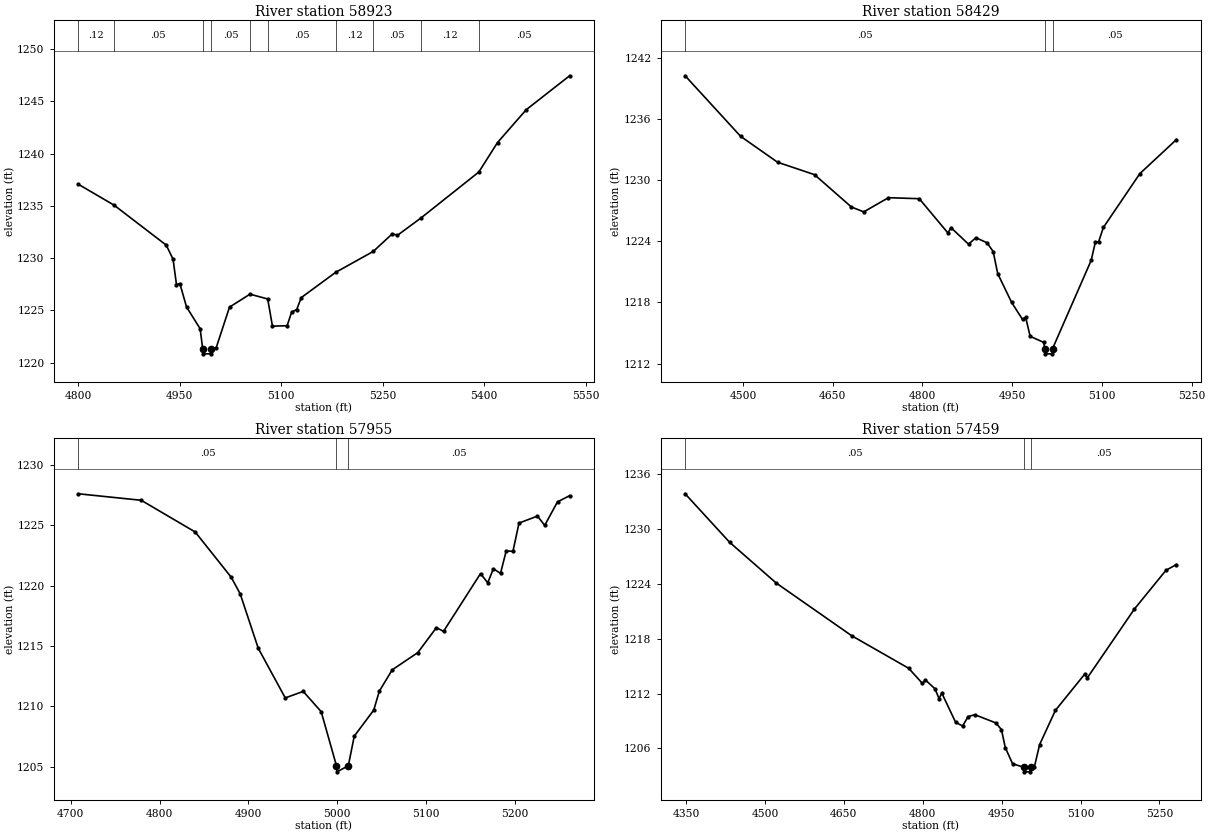
Type RM Length L Ch R = 1,58923,494,494,494
BEGIN DESCRIPTION:
WRIGHTS CREEK 105.0
END DESCRIPTION:
XS GIS Cut Line= 3
      2819555.73     10276403.11      2819355.75     10276410.00
      2819005.68     10276803.12
#Sta/Elev= 30
  4799.9 1237.06  4852.8 1235.06  4930.0 1231.23  4940.0 1229.89  4945.1 1227.46
  4950.1 1227.55  4960.0 1225.31  4980.1 1223.23  4983.8 1221.33  4984.3 1220.83
  4995.9 1220.83  4996.4 1221.33  5003.8 1221.41  5023.5 1225.30  5053.8 1226.54
  5080.0 1226.08  5087.0 1223.48  5108.7 1223.52  5115.4 1224.83  5122.9 1225.07
  5129.6 1226.21  5180.5 1228.63  5236.1 1230.63  5264.3 1232.32  5271.8 1232.17
  5307.2 1233.86  5392.2 1238.23  5419.8 1241.05  5462.4 1244.20  5526.4 1247.44
#Mann=10,-1,0
  4799.9    0.12       0  4852.8    0.05       0  4983.8    0.05       0
  4996.4    0.05       0  5053.8    0.12       0  5080.0    0.05       0
  5180.5    0.12       0  5236.1    0.05       0  5307.2    0.12       0
  5392.2    0.05       0
Bank Sta=4983.8,4996.4
Exp/Cntr=0.3,0.1

Type RM Length L Ch R = 1,58429,474,474,474
BEGIN DESCRIPTION:
WRIGHTS CREEK 104.0
END DESCRIPTION:
XS GIS Cut Line= 3
      2819655.68     10276153.11      2819076.25     10276011.00
      2818855.73     10276053.10
#Sta/Elev= 30
  4403.4 1240.23  4496.1 1234.29  4557.8 1231.75  4619.6 1230.53  4681.4 1227.35
  4702.0 1226.88  4743.2 1228.27  4794.7 1228.17  4842.6 1224.81  4847.7 1225.33
  4877.0 1223.71  4889.3 1224.34  4907.9 1223.85  4918.2 1222.99  4925.8 1220.82
  4949.1 1217.99  4967.3 1216.32  4972.5 1216.53  4980.0 1214.67  5002.8 1214.07
  5004.2 1213.45  5004.7 1212.95  5016.9 1212.95  5017.4 1213.45  5082.0 1222.12
  5089.2 1223.96  5094.3 1223.92  5102.4 1225.35  5163.5 1230.64  5224.5 1233.97
#Mann=3,-1,0
  4403.4    0.05       0  5004.2    0.03       0  5017.4    0.05       0
Bank Sta=5004.2,5017.4
Exp/Cntr=0.3,0.1

Type RM Length L Ch R = 1,57955,496,496,496
BEGIN DESCRIPTION:
WRIGHTS CREEK 103.0
END DESCRIPTION:
XS GIS Cut Line= 3
      2819405.64     10275603.10      2819117.75     10275558.00
      2818955.71     10275353.14
#Sta/Elev= 30
  4708.6 1227.63  4779.4 1227.09  4840.1 1224.46  4880.6 1220.71  4890.7 1219.33
  4911.0 1214.82  4941.4 1210.70  4961.6 1211.24  4981.8 1209.56  4999.0 1205.07
  4999.5 1204.57  5012.3 1205.07  5019.0 1207.53  5040.9 1209.69  5047.2 1211.26
  5061.7 1213.03  5090.5 1214.46  5111.4 1216.53  5119.4 1216.22  5161.0 1221.01
  5169.1 1220.25  5175.5 1221.41  5183.5 1221.03  5189.9 1222.89  5197.5 1222.86
  5204.3 1225.20  5225.1 1225.78  5233.2 1225.01  5247.6 1226.96  5261.2 1227.47
#Mann=3,-1,0
  4708.6    0.05       0  4999.0    0.05       0  5012.3    0.05       0
Bank Sta=4999,5012.3
Exp/Cntr=0.3,0.1

Type RM Length L Ch R = 1,57459,485,485,485
BEGIN DESCRIPTION:
WRIGHTS CREEK 102.0
END DESCRIPTION:
XS GIS Cut Line= 3
      2819905.68     10275303.11      2819288.00     10275095.00
      2819005.72     10275103.11
#Sta/Elev= 30
  4348.2 1233.86  4432.6 1228.56  4521.4 1224.09  4664.8 1218.33  4773.3 1214.76
  4799.5 1213.10  4804.8 1213.50  4823.1 1212.53  4831.0 1211.45  4836.3 1212.04
  4862.5 1208.85  4875.8 1208.45  4886.4 1209.48  4899.2 1209.68  4939.1 1208.78
  4949.7 1208.05  4956.9 1206.09  4970.8 1204.32  4991.9 1203.93  4992.4 1203.43
  5004.7 1203.43  5005.2 1203.93  5012.3 1203.98  5022.3 1206.42  5052.3 1210.16
  5107.8 1214.11  5112.9 1213.71  5202.4 1221.24  5262.4 1225.48  5282.4 1226.12
#Mann=3,-1,0
  4348.2    0.05       0  4991.9    0.05       0  5005.2    0.05       0
Bank Sta=4991.9,5005.2
Exp/Cntr=0.3,0.1