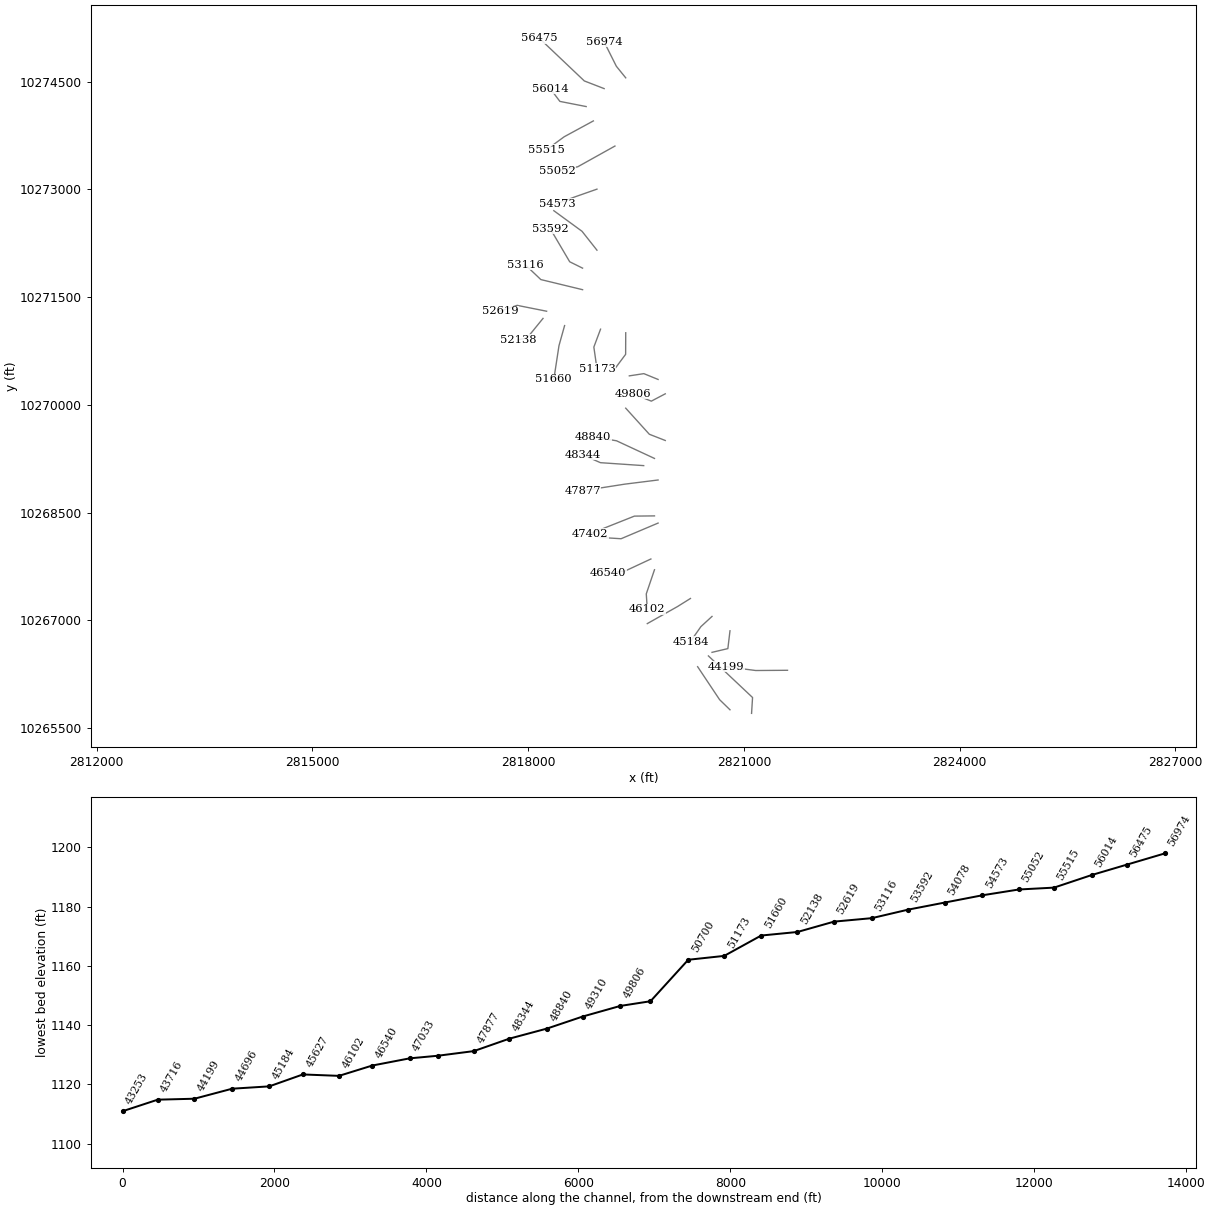
HEC-RAS study WRIGHTS CREEK.prj: WRIGHTS CREEK Base Level Engineering

--- WRIGHTS CREEK.g01 (geometry) --- (continued)

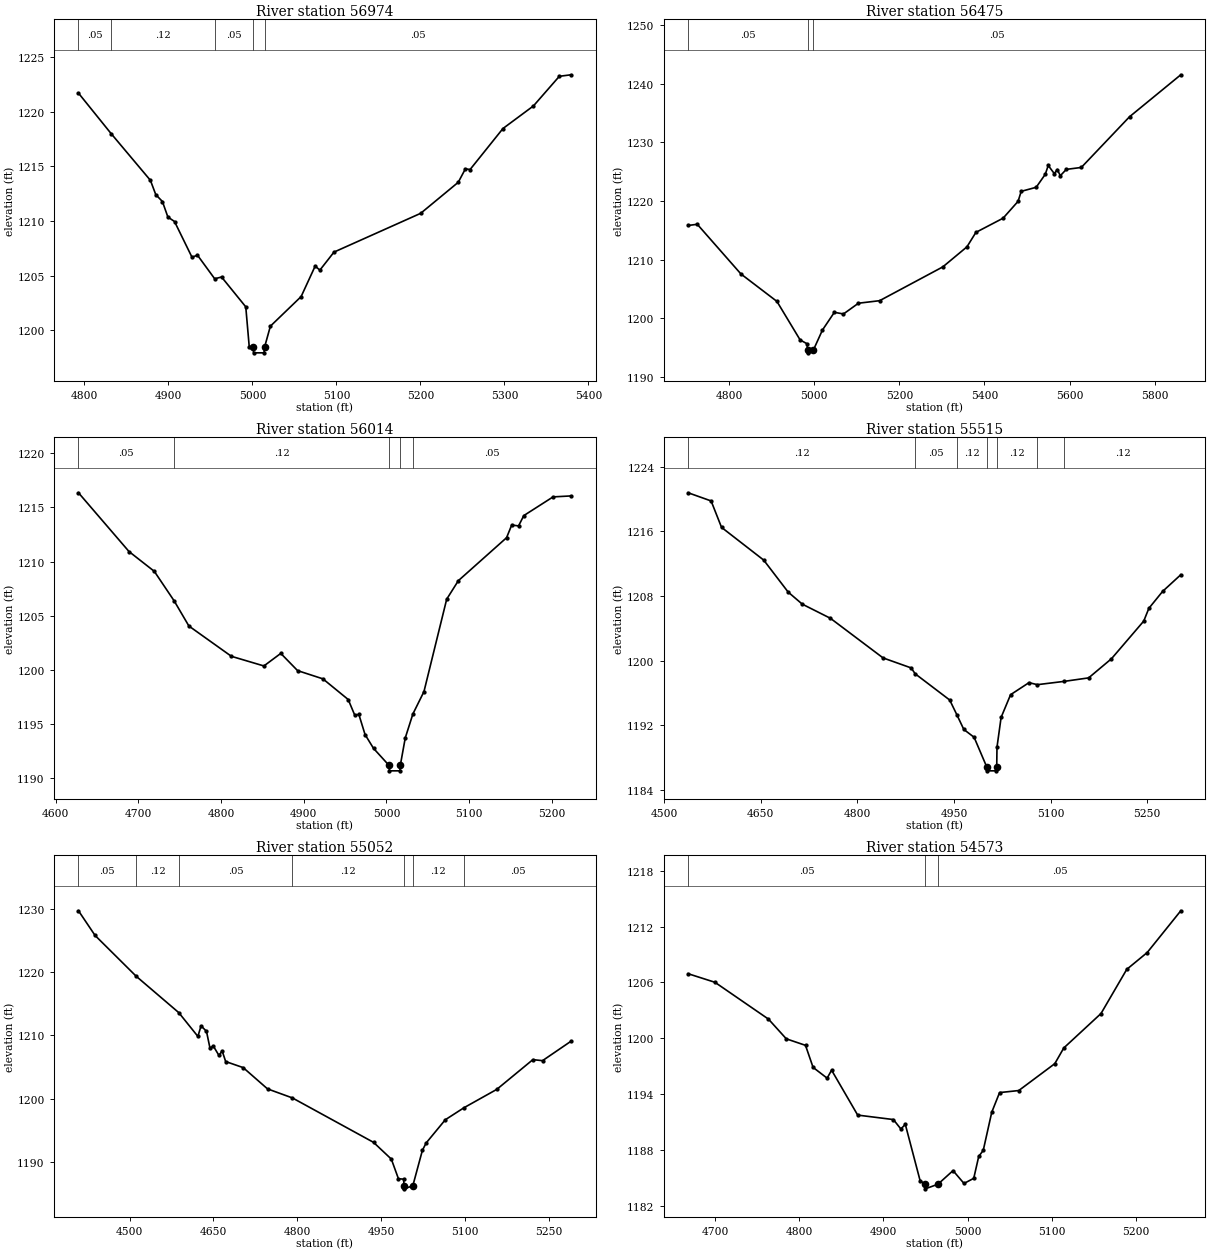
Type RM Length L Ch R = 1,56974,499,499,499
BEGIN DESCRIPTION:
WRIGHTS CREEK 101.0
END DESCRIPTION:
XS GIS Cut Line= 3
      2819355.71     10274553.08      2819225.50     10274714.00
      2819055.66     10275053.15
#Sta/Elev= 30
  4793.0 1221.70  4831.8 1218.00  4878.6 1213.72  4885.0 1212.41  4892.9 1211.78
  4899.4 1210.36  4907.3 1209.95  4928.1 1206.68  4934.6 1206.87  4955.1 1204.71
  4963.3 1204.87  4992.1 1202.14  4996.2 1198.51  5000.9 1198.43  5001.4 1197.93
  5013.9 1197.93  5014.4 1198.43  5021.4 1200.37  5058.0 1203.08  5074.7 1205.87
  5080.3 1205.50  5097.1 1207.15  5200.3 1210.70  5245.0 1213.54  5253.5 1214.77
  5259.1 1214.71  5298.2 1218.46  5334.5 1220.53  5365.3 1223.24  5379.3 1223.38
#Mann=5,-1,0
  4793.0    0.05       0  4831.8    0.12       0  4955.1    0.05       0
  5000.9    0.05       0  5014.4    0.05       0
Bank Sta=5000.9,5014.4
Exp/Cntr=0.3,0.1

Type RM Length L Ch R = 1,56475,461,461,461
BEGIN DESCRIPTION:
WRIGHTS CREEK 100.0
END DESCRIPTION:
XS GIS Cut Line= 3
      2819055.67     10274403.12      2818779.75     10274510.00
      2818155.65     10275103.14
#Sta/Elev= 30
  4704.1 1215.84  4725.5 1216.04  4828.0 1207.58  4912.5 1202.91  4967.0 1196.35
  4982.9 1195.71  4984.7 1194.65  4985.2 1194.15  4998.3 1194.65  5019.4 1198.03
  5047.4 1201.05  5068.8 1200.77  5104.0 1202.60  5153.7 1203.03  5302.2 1208.79
  5358.8 1212.20  5379.8 1214.66  5443.7 1217.08  5478.9 1219.95  5486.2 1221.65
  5521.4 1222.34  5542.8 1224.56  5549.7 1226.06  5563.9 1224.67  5571.1 1225.37
  5578.0 1224.31  5592.2 1225.39  5627.4 1225.72  5740.6 1234.35  5861.0 1241.50
#Mann=3,-1,0
  4704.1    0.05       0  4984.7    0.05       0  4998.3    0.05       0
Bank Sta=4984.7,4998.3
Exp/Cntr=0.3,0.1

Type RM Length L Ch R = 1,56014,499,499,499
BEGIN DESCRIPTION:
WRIGHTS CREEK 99.0
END DESCRIPTION:
XS GIS Cut Line= 3
      2818805.65     10274153.12      2818440.25     10274225.00
      2818305.70     10274403.09
#Sta/Elev= 30
  4627.6 1216.35  4688.7 1210.92  4719.3 1209.09  4743.3 1206.36  4761.1 1204.04
  4812.5 1201.24  4851.8 1200.35  4872.2 1201.51  4892.5 1199.92  4923.1 1199.16
  4953.7 1197.25  4961.6 1195.81  4966.6 1195.87  4974.1 1194.01  4984.3 1192.74
  5003.1 1191.16  5003.6 1190.66  5016.2 1190.66  5016.7 1191.16  5022.7 1193.70
  5031.9 1195.91  5045.3 1197.98  5072.8 1206.52  5086.9 1208.23  5145.2 1212.20
  5151.4 1213.37  5159.7 1213.29  5166.0 1214.24  5201.4 1215.97  5223.2 1216.06
#Mann=5,-1,0
  4627.6    0.05       0  4743.3    0.12       0  5003.1    0.07       0
  5016.7    0.12       0  5031.9    0.05       0
Bank Sta=5003.1,5016.7
Exp/Cntr=0.3,0.1

Type RM Length L Ch R = 1,55515,463,463,463
BEGIN DESCRIPTION:
WRIGHTS CREEK 98.0
END DESCRIPTION:
XS GIS Cut Line= 3
      2818905.70     10273953.12      2818499.25     10273732.00
      2818255.68     10273553.11
#Sta/Elev= 30
  4537.3 1220.79  4572.9 1219.78  4589.1 1216.51  4654.6 1212.46  4692.6 1208.50
  4714.5 1207.01  4758.2 1205.26  4839.9 1200.36  4883.6 1199.12  4889.7 1198.40
  4943.4 1195.15  4954.9 1193.26  4965.3 1191.51  4981.3 1190.54  5000.8 1186.89
  5001.3 1186.39  5015.9 1186.39  5016.4 1186.89  5016.8 1189.31  5023.2 1193.00
  5037.9 1195.81  5066.5 1197.30  5079.5 1197.05  5121.3 1197.46  5159.1 1197.89
  5194.6 1200.26  5244.7 1204.92  5252.6 1206.49  5274.0 1208.59  5302.2 1210.65
#Mann=7,-1,0
  4537.3    0.12       0  4889.7    0.05       0  4954.9    0.12       0
  5000.8    0.07       0  5016.4    0.12       0  5079.5    0.05       0
  5121.3    0.12       0
Bank Sta=5000.8,5016.4
Exp/Cntr=0.3,0.1

Type RM Length L Ch R = 1,55052,479,479,479
BEGIN DESCRIPTION:
WRIGHTS CREEK 97.0
END DESCRIPTION:
XS GIS Cut Line= 3
      2819205.71     10273603.13      2818689.25     10273315.00
      2818405.72     10273253.12
#Sta/Elev= 30
  4408.6 1229.71  4438.3 1225.81  4511.9 1219.36  4588.1 1213.61  4622.3 1209.85
  4628.0 1211.53  4637.7 1210.65  4644.0 1207.97  4649.8 1208.35  4660.0 1206.84
  4665.7 1207.57  4672.0 1205.88  4703.4 1204.92  4746.9 1201.56  4791.4 1200.13
  4936.6 1193.11  4968.5 1190.46  4981.2 1187.36  4990.3 1187.29  4991.4 1186.26
  4991.9 1185.76  5007.0 1186.26  5024.1 1191.85  5030.8 1193.01  5065.1 1196.68
  5098.5 1198.58  5157.2 1201.48  5221.8 1206.18  5239.1 1206.02  5290.2 1209.10
#Mann=7,-1,0
  4408.6    0.05       0  4511.9    0.12       0  4588.1    0.05       0
  4791.4    0.12       0  4991.4    0.07       0  5007.0    0.12       0
  5098.5    0.05       0
Bank Sta=4991.4,5007
Exp/Cntr=0.3,0.1

Type RM Length L Ch R = 1,54573,495,495,495
BEGIN DESCRIPTION:
WRIGHTS CREEK 96.0
END DESCRIPTION:
XS GIS Cut Line= 3
      2818955.71     10273003.12      2818642.50     10272893.00
      2818405.69     10272803.11
#Sta/Elev= 30
  4668.0 1206.94  4699.8 1206.02  4763.4 1202.06  4784.6 1199.94  4807.4 1199.24
  4816.4 1196.87  4833.1 1195.71  4838.4 1196.57  4869.4 1191.74  4911.8 1191.26
  4920.7 1190.25  4926.0 1190.74  4943.6 1184.68  4949.2 1184.31  4949.7 1183.81
  4964.8 1184.31  4982.7 1185.77  4995.7 1184.39  5007.3 1184.94  5013.2 1187.29
  5018.6 1187.95  5028.7 1192.05  5038.0 1194.16  5060.8 1194.38  5103.6 1197.27
  5114.3 1198.96  5158.5 1202.66  5189.1 1207.41  5213.4 1209.22  5253.3 1213.71
#Mann=3,-1,0
  4668.0    0.05       0  4949.2    0.03       0  4964.8    0.05       0
Bank Sta=4949.2,4964.8
Exp/Cntr=0.3,0.1

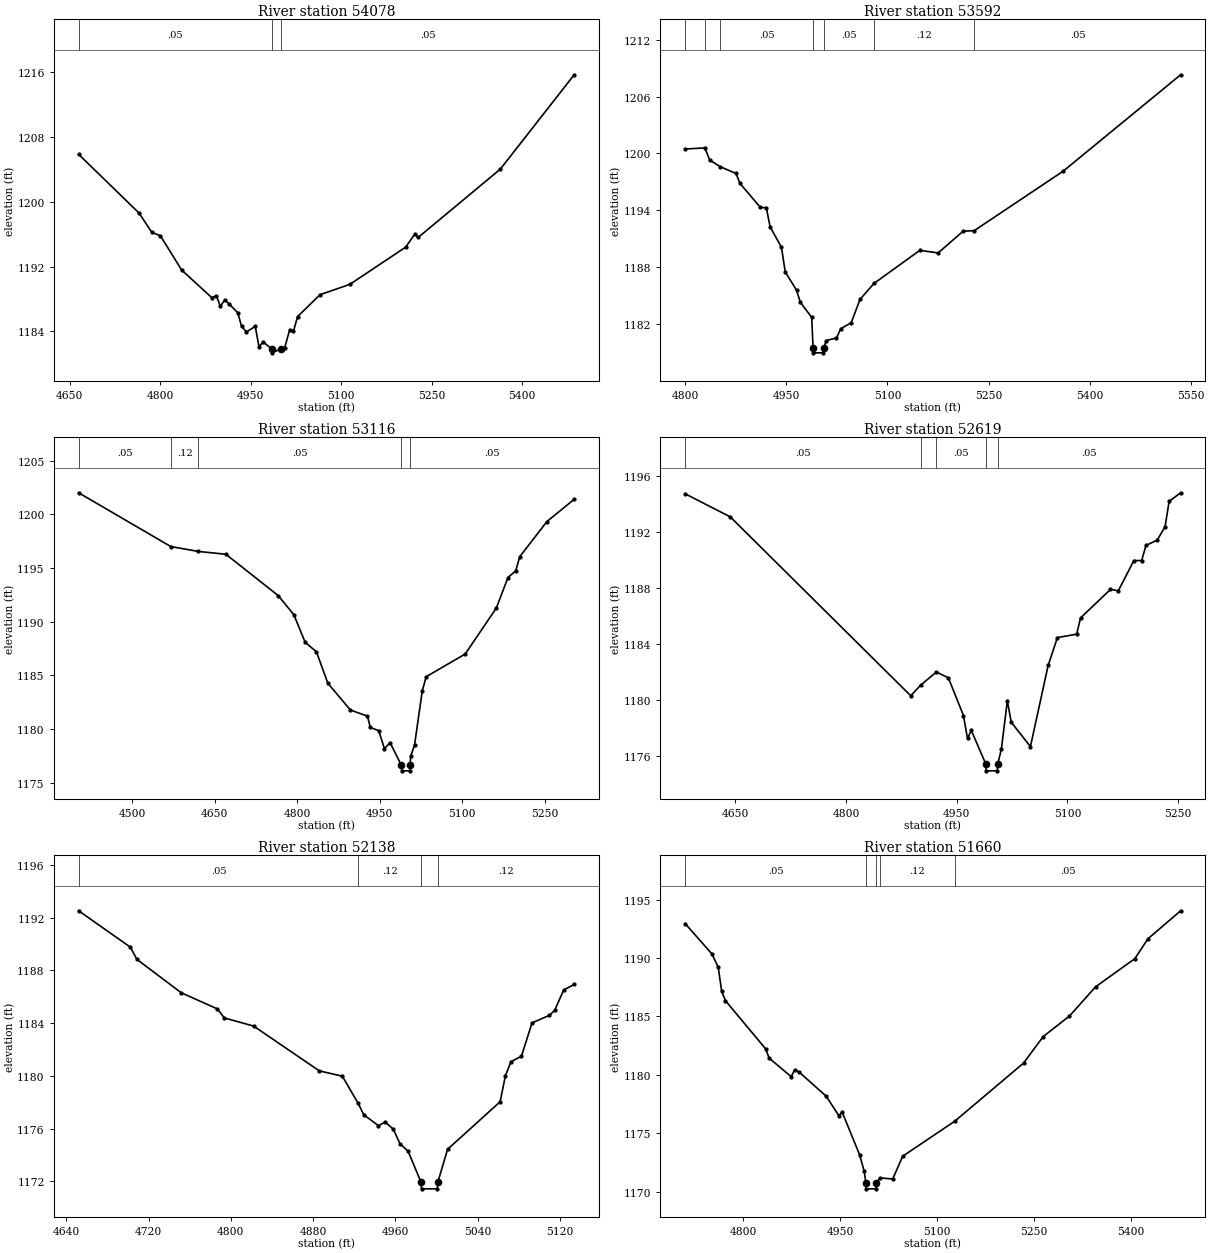
Type RM Length L Ch R = 1,54078,486,486,486
BEGIN DESCRIPTION:
WRIGHTS CREEK 95.0
END DESCRIPTION:
XS GIS Cut Line= 3
      2818955.70     10272153.09      2818748.25     10272416.00
      2818355.65     10272703.14
#Sta/Elev= 30
  4665.1 1205.85  4765.4 1198.59  4786.2 1196.24  4800.6 1195.80  4835.9 1191.57
  4885.6 1188.18  4893.6 1188.38  4900.0 1187.08  4907.2 1187.90  4914.4 1187.40
  4928.9 1186.30  4935.2 1184.61  4943.3 1183.94  4957.8 1184.63  4964.1 1182.09
  4970.8 1182.70  4985.1 1181.86  4985.6 1181.36  5000.9 1181.86  5006.5 1181.95
  5014.9 1184.22  5021.1 1184.02  5028.0 1185.83  5065.1 1188.53  5114.7 1189.81
  5207.2 1194.40  5221.9 1195.98  5228.1 1195.61  5364.0 1204.02  5486.4 1215.66
#Mann=3,-1,0
  4665.1    0.05       0  4985.1    0.05       0  5000.9    0.05       0
Bank Sta=4985.1,5000.9
Exp/Cntr=0.3,0.1

Type RM Length L Ch R = 1,53592,476,476,476
BEGIN DESCRIPTION:
WRIGHTS CREEK 94.0
END DESCRIPTION:
XS GIS Cut Line= 3
      2818755.67     10271903.12      2818576.50     10271992.00
      2818305.66     10272453.15
#Sta/Elev= 30
  4800.0 1200.47  4829.3 1200.59  4836.4 1199.32  4852.4 1198.59  4875.6 1197.89
  4881.2 1196.86  4911.6 1194.30  4920.5 1194.27  4926.0 1192.26  4942.9 1190.09
  4948.5 1187.49  4965.3 1185.56  4970.9 1184.28  4987.7 1182.70  4989.8 1179.45
  4990.3 1178.95  5005.1 1178.95  5005.6 1179.45  5009.3 1180.25  5024.5 1180.52
  5030.8 1181.50  5046.4 1182.13  5059.3 1184.59  5080.1 1186.28  5148.0 1189.77
  5175.2 1189.50  5212.4 1191.80  5228.7 1191.85  5360.8 1198.14  5534.8 1208.31
#Mann=7,-1,0
  4800.0    0.05       0  4829.3    0.12       0  4852.4    0.05       0
  4989.8    0.03       0  5005.6    0.05       0  5080.1    0.12       0
  5228.7    0.05       0
Bank Sta=4989.8,5005.6
Exp/Cntr=0.3,0.1

Type RM Length L Ch R = 1,53116,497,497,497
BEGIN DESCRIPTION:
WRIGHTS CREEK 93.0
END DESCRIPTION:
XS GIS Cut Line= 3
      2818755.70     10271603.11      2818175.25     10271744.00
      2817955.69     10271953.10
#Sta/Elev= 30
  4402.7 1202.01  4570.1 1197.00  4620.4 1196.54  4670.3 1196.28  4765.5 1192.42
  4793.7 1190.65  4814.3 1188.08  4834.9 1187.18  4855.5 1184.26  4896.6 1181.76
  4927.5 1181.19  4932.7 1180.14  4948.1 1179.83  4958.4 1178.16  4968.7 1178.72
  4989.3 1176.59  4989.8 1176.09  5004.7 1176.09  5005.2 1176.59  5006.1 1177.43
  5013.2 1178.52  5027.2 1183.56  5034.4 1184.87  5105.2 1186.98  5161.8 1191.27
  5182.9 1194.11  5197.0 1194.74  5204.3 1196.05  5253.7 1199.33  5303.2 1201.40
#Mann=5,-1,0
  4402.7    0.05       0  4570.1    0.12       0  4620.4    0.05       0
  4989.3    0.03       0  5005.2    0.05       0
Bank Sta=4989.3,5005.2
Exp/Cntr=0.3,0.1

Type RM Length L Ch R = 1,52619,481,481,481
BEGIN DESCRIPTION:
WRIGHTS CREEK 92.0
END DESCRIPTION:
XS GIS Cut Line= 3
      2818255.71     10271303.11      2817845.50     10271385.00
      2817605.69     10271303.12
#Sta/Elev= 30
  4581.7 1194.71  4642.9 1193.06  4887.6 1180.28  4900.8 1181.03  4922.3 1181.98
  4938.6 1181.56  4959.0 1178.87  4964.5 1177.23  4969.6 1177.81  4989.2 1175.42
  4989.7 1174.92  5005.0 1174.92  5005.5 1175.42  5010.4 1176.46  5018.5 1179.93
  5023.8 1178.39  5049.8 1176.65  5073.8 1182.45  5086.4 1184.44  5112.5 1184.68
  5117.7 1185.84  5158.3 1187.88  5168.9 1187.78  5190.0 1189.94  5200.6 1189.94
  5206.4 1191.02  5221.7 1191.40  5232.3 1192.36  5237.8 1194.17  5253.4 1194.78
#Mann=5,-1,0
  4581.7    0.05       0  4900.8    0.12       0  4922.3    0.05       0
  4989.2    0.05       0  5005.5    0.05       0
Bank Sta=4989.2,5005.5
Exp/Cntr=0.3,0.1

Type RM Length L Ch R = 1,52138,478,478,478
BEGIN DESCRIPTION:
WRIGHTS CREEK 91.0
END DESCRIPTION:
XS GIS Cut Line= 3
      2818205.68     10271203.10      2817986.25     10270933.00
      2817855.73     10270903.12
#Sta/Elev= 30
  4652.0 1192.53  4702.3 1189.77  4708.7 1188.84  4751.8 1186.31  4787.0 1185.08
  4793.7 1184.40  4822.2 1183.78  4886.1 1180.38  4908.4 1179.98  4923.9 1177.91
  4929.3 1177.05  4943.6 1176.22  4950.1 1176.50  4958.0 1175.96  4964.4 1174.87
  4972.4 1174.28  4985.0 1171.93  4985.5 1171.43  5000.8 1171.43  5001.3 1171.93
  5010.8 1174.43  5061.9 1178.04  5067.0 1180.00  5072.4 1181.08  5082.6 1181.49
  5092.9 1184.02  5109.9 1184.60  5115.0 1184.98  5123.7 1186.52  5133.9 1186.94
#Mann=4,-1,0
  4652.0    0.05       0  4923.9    0.12       0  4985.0    0.07       0
  5001.3    0.12       0
Bank Sta=4985,5001.3
Exp/Cntr=0.3,0.1

Type RM Length L Ch R = 1,51660,487,487,487
BEGIN DESCRIPTION:
WRIGHTS CREEK 90.0
END DESCRIPTION:
XS GIS Cut Line= 3
      2818505.69     10271103.12      2818427.75     10270824.00
      2818355.68     10270353.08
#Sta/Elev= 30
  4710.2 1192.95  4751.7 1190.34  4761.5 1189.19  4766.7 1187.15  4772.5 1186.35
  4834.8 1182.21  4840.2 1181.42  4874.3 1179.83  4879.5 1180.42  4886.7 1180.22
  4928.2 1178.17  4947.9 1176.50  4953.1 1176.80  4980.2 1173.12  4987.2 1171.72
  4989.7 1170.73  4990.2 1170.23  5005.6 1170.23  5006.1 1170.73  5011.7 1171.17
  5031.2 1171.07  5046.6 1173.02  5127.1 1176.02  5233.6 1181.00  5263.9 1183.27
  5304.4 1185.02  5344.9 1187.53  5405.6 1189.94  5425.8 1191.64  5476.4 1194.04
#Mann=5,-1,0
  4710.2    0.05       0  4989.7    0.03       0  5006.1    0.05       0
  5011.7    0.12       0  5127.1    0.05       0
Bank Sta=4989.7,5006.1
Exp/Cntr=0.3,0.1

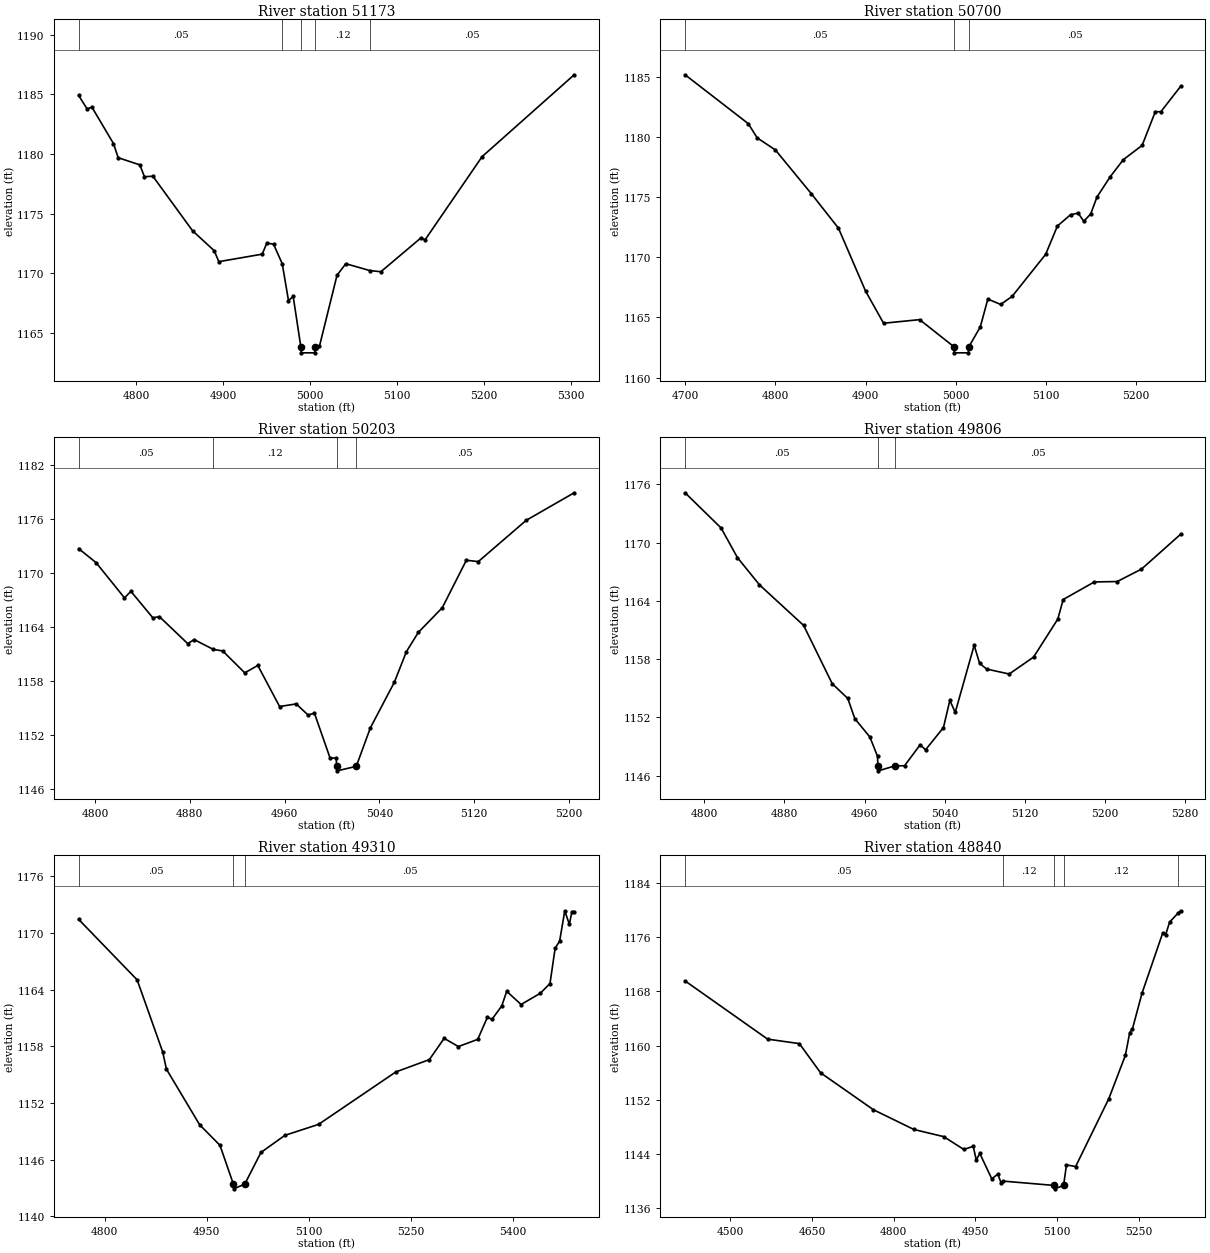
Type RM Length L Ch R = 1,51173,473,473,473
BEGIN DESCRIPTION:
WRIGHTS CREEK 89.0
END DESCRIPTION:
XS GIS Cut Line= 3
      2819005.69     10271053.14      2818912.50     10270804.00
      2818955.69     10270503.08
#Sta/Elev= 30
  4734.0 1184.90  4743.8 1183.77  4749.2 1183.93  4774.1 1180.87  4779.5 1179.69
  4804.4 1179.09  4809.7 1178.10  4819.4 1178.14  4865.0 1173.58  4889.9 1171.91
  4895.3 1170.99  4945.2 1171.62  4950.5 1172.55  4958.2 1172.45  4968.2 1170.82
  4975.4 1167.73  4980.8 1168.08  4989.6 1163.86  4990.1 1163.36  5005.5 1163.36
  5006.0 1163.86  5011.0 1163.91  5031.2 1169.85  5041.3 1170.82  5069.2 1170.24
  5081.7 1170.15  5127.6 1172.97  5132.6 1172.83  5198.1 1179.78  5304.0 1186.63
#Mann=5,-1,0
  4734.0    0.05       0  4968.2    0.12       0  4989.6    0.07       0
  5006.0    0.12       0  5069.2    0.05       0
Bank Sta=4989.6,5006
Exp/Cntr=0.3,0.1

Type RM Length L Ch R = 1,50700,497,497,497
BEGIN DESCRIPTION:
WRIGHTS CREEK 88.0
END DESCRIPTION:
XS GIS Cut Line= 3
      2819355.68     10271003.10      2819354.50     10270703.00
      2819205.69     10270503.11
#Sta/Elev= 30
  4699.9 1185.17  4769.9 1181.11  4779.9 1179.92  4799.9 1178.93  4839.9 1175.28
  4869.9 1172.42  4899.9 1167.20  4919.9 1164.52  4959.9 1164.82  4998.0 1162.56
  4998.5 1162.06  5013.9 1162.06  5014.4 1162.56  5027.1 1164.21  5035.5 1166.53
  5049.7 1166.08  5062.5 1166.76  5099.6 1170.25  5112.6 1172.60  5127.2 1173.54
  5135.6 1173.67  5141.8 1173.00  5149.5 1173.60  5156.4 1175.00  5171.0 1176.68
  5185.6 1178.11  5206.5 1179.30  5221.1 1182.10  5227.3 1182.10  5249.2 1184.21
#Mann=3,-1,0
  4699.9    0.05       0  4998.0    0.05       0  5014.4    0.05       0
Bank Sta=4998,5014.4
Exp/Cntr=0.3,0.1

Type RM Length L Ch R = 1,50203,397,397,397
BEGIN DESCRIPTION:
WRIGHTS CREEK 87.0
END DESCRIPTION:
XS GIS Cut Line= 3
      2819805.66     10270353.12      2819607.75     10270434.00
      2819405.70     10270403.11
#Sta/Elev= 30
  4786.2 1172.74  4800.9 1171.19  4824.9 1167.27  4830.3 1168.00  4848.9 1165.05
  4854.3 1165.20  4878.3 1162.19  4883.7 1162.64  4899.9 1161.55  4907.8 1161.38
  4926.4 1158.95  4937.4 1159.77  4955.8 1155.21  4969.8 1155.50  4979.8 1154.27
  4985.2 1154.47  4998.4 1149.49  5003.6 1149.49  5003.9 1148.57  5004.4 1148.07
  5020.5 1148.57  5032.4 1152.84  5052.7 1157.92  5062.8 1161.30  5072.9 1163.44
  5093.1 1166.18  5113.4 1171.45  5123.5 1171.30  5163.9 1175.88  5204.4 1178.94
#Mann=4,-1,0
  4786.2    0.05       0  4899.9    0.12       0  5003.9    0.07       0
  5020.5    0.05       0
Bank Sta=5003.9,5020.5
Exp/Cntr=0.3,0.1

Type RM Length L Ch R = 1,49806,496,496,496
BEGIN DESCRIPTION:
WRIGHTS CREEK 86.0
END DESCRIPTION:
XS GIS Cut Line= 3
      2819905.71     10270153.12      2819711.75     10270051.00
      2819455.66     10270153.12
#Sta/Elev= 30
  4780.8 1175.12  4816.7 1171.50  4833.1 1168.44  4855.1 1165.64  4899.2 1161.46
  4927.7 1155.47  4943.3 1153.94  4950.3 1151.86  4965.3 1149.98  4973.0 1147.98
  4973.3 1146.99  4973.8 1146.49  4990.0 1146.99  5000.0 1147.02  5015.6 1149.18
  5020.9 1148.65  5038.8 1150.94  5045.2 1153.74  5050.6 1152.51  5069.5 1159.42
  5074.9 1157.57  5081.9 1156.97  5104.5 1156.46  5128.8 1158.20  5153.0 1162.11
  5158.4 1164.13  5189.5 1165.94  5212.3 1165.98  5236.6 1167.26  5275.7 1170.85
#Mann=3,-1,0
  4780.8    0.05       0  4973.3    0.05       0  4990.0    0.05       0
Bank Sta=4973.3,4990
Exp/Cntr=0.3,0.1

Type RM Length L Ch R = 1,49310,470,470,470
BEGIN DESCRIPTION:
WRIGHTS CREEK 85.0
END DESCRIPTION:
XS GIS Cut Line= 3
      2819905.68     10269503.11      2819684.00     10269590.00
      2819355.71     10269953.09
#Sta/Elev= 30
  4761.9 1171.43  4847.8 1165.03  4885.3 1157.41  4890.8 1155.58  4939.6 1149.69
  4969.4 1147.52  4989.1 1143.41  4989.6 1142.91  5005.8 1143.41  5029.6 1146.76
  5064.7 1148.57  5114.1 1149.73  5227.6 1155.28  5276.9 1156.59  5298.6 1158.84
  5319.5 1157.97  5347.9 1158.73  5362.1 1161.07  5368.9 1160.86  5383.1 1162.26
  5390.5 1163.82  5411.5 1162.42  5439.8 1163.61  5454.0 1164.64  5461.5 1168.35
  5468.2 1169.15  5475.7 1172.34  5482.4 1170.90  5486.2 1172.25  5489.5 1172.25
#Mann=3,-1,0
  4761.9    0.05       0  4989.1    0.03       0  5005.8    0.05       0
Bank Sta=4989.1,5005.8
Exp/Cntr=0.3,0.1

Type RM Length L Ch R = 1,48840,496,496,496
BEGIN DESCRIPTION:
WRIGHTS CREEK 84.0
END DESCRIPTION:
XS GIS Cut Line= 3
      2819755.67     10269253.12      2819227.50     10269499.00
      2818905.72     10269553.11
#Sta/Elev= 30
  4417.4 1169.56  4568.8 1160.96  4627.0 1160.30  4665.9 1155.99  4762.9 1150.53
  4837.0 1147.62  4891.7 1146.56  4928.6 1144.67  4945.9 1145.13  4951.4 1143.12
  4957.9 1144.08  4979.9 1140.33  4991.0 1141.02  4997.2 1139.68  5001.0 1139.99
  5094.8 1139.35  5095.3 1138.85  5111.6 1139.35  5116.9 1142.39  5133.7 1142.14
  5194.5 1152.16  5224.9 1158.56  5232.9 1161.91  5238.0 1162.50  5255.4 1167.73
  5293.5 1176.66  5298.6 1176.33  5306.1 1178.25  5321.8 1179.60  5326.3 1179.92
#Mann=5,-1,0
  4417.4    0.05       0  5001.0    0.12       0  5094.8    0.05       0
  5111.6    0.12       0  5321.8    0.05       0
Bank Sta=5094.8,5111.6
Exp/Cntr=0.3,0.1

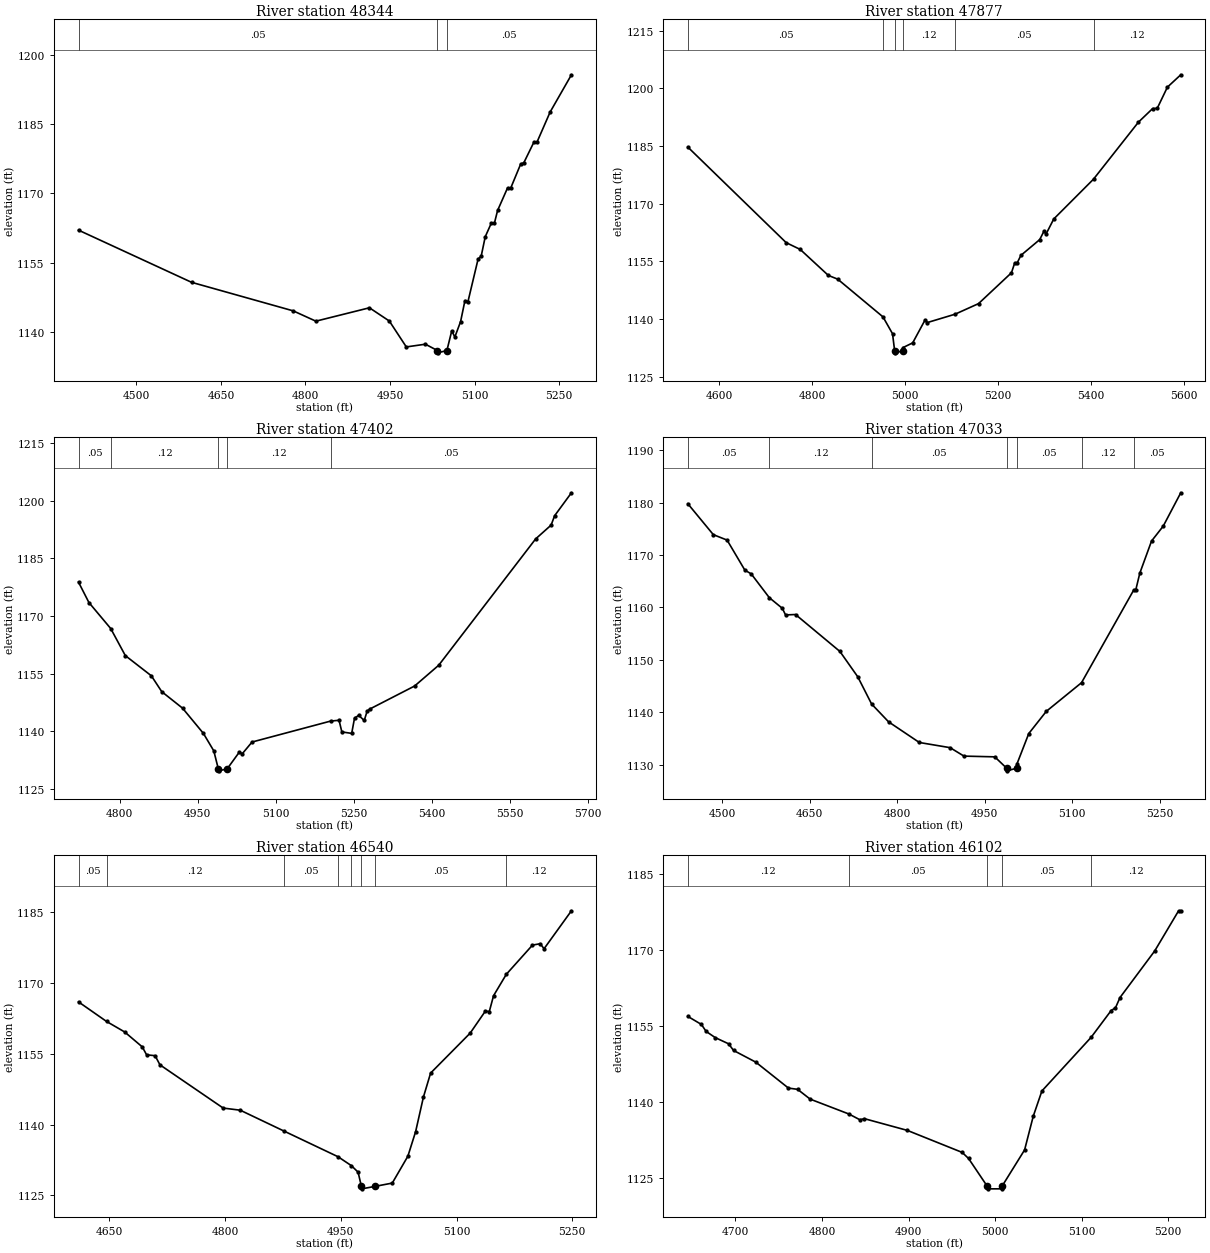
Type RM Length L Ch R = 1,48344,467,467,467
BEGIN DESCRIPTION:
WRIGHTS CREEK 83.0
END DESCRIPTION:
XS GIS Cut Line= 3
      2819605.71     10269153.11      2819004.50     10269194.00
      2818755.67     10269303.12
#Sta/Elev= 30
  4397.4 1162.02  4597.9 1150.72  4778.3 1144.53  4818.4 1142.30  4913.4 1145.20
  4948.7 1142.33  4978.8 1136.72  5012.7 1137.31  5034.0 1135.94  5034.5 1135.44
  5050.8 1135.94  5059.4 1140.21  5064.9 1138.87  5075.1 1142.21  5082.8 1146.76
  5088.2 1146.55  5106.1 1155.75  5111.6 1156.37  5118.8 1160.59  5129.5 1163.52
  5135.0 1163.50  5140.7 1166.28  5158.3 1171.15  5163.8 1171.08  5181.7 1176.35
  5187.2 1176.61  5205.1 1181.08  5210.5 1181.06  5233.9 1187.61  5271.7 1195.68
#Mann=3,-1,0
  4397.4    0.05       0  5034.0    0.05       0  5050.8    0.05       0
Bank Sta=5034,5050.8
Exp/Cntr=0.3,0.1

Type RM Length L Ch R = 1,47877,475,475,475
BEGIN DESCRIPTION:
WRIGHTS CREEK 82.0
END DESCRIPTION:
XS GIS Cut Line= 3
      2819805.72     10268953.12      2819341.75     10268895.00
      2818755.71     10268803.12
#Sta/Elev= 30
  4532.4 1184.72  4744.1 1159.88  4774.3 1158.12  4834.8 1151.37  4854.9 1150.40
  4952.4 1140.59  4972.9 1136.22  4977.5 1131.75  4978.0 1131.25  4994.4 1131.75
  4995.5 1132.62  5016.3 1133.84  5043.0 1139.81  5048.1 1139.13  5107.5 1141.29
  5158.0 1144.04  5228.8 1152.05  5236.0 1154.66  5241.1 1154.61  5249.1 1156.57
  5289.6 1160.67  5298.7 1162.83  5303.7 1162.22  5319.9 1166.04  5405.4 1176.38
  5502.1 1191.20  5532.5 1194.71  5542.6 1194.80  5564.4 1200.29  5593.2 1203.51
#Mann=6,-1,0
  4532.4    0.05       0  4952.4    0.12       0  4977.5    0.07       0
  4994.4    0.12       0  5107.5    0.05       0  5405.4    0.12       0
Bank Sta=4977.5,4994.4
Exp/Cntr=0.3,0.1

Type RM Length L Ch R = 1,47402,369,369,369
BEGIN DESCRIPTION:
WRIGHTS CREEK 81.0
END DESCRIPTION:
XS GIS Cut Line= 3
      2819755.68     10268453.11      2819476.50     10268450.00
      2818855.69     10268203.11
#Sta/Elev= 30
  4720.8 1178.81  4740.8 1173.50  4782.7 1166.73  4810.8 1159.68  4860.8 1154.42
  4880.8 1150.29  4920.8 1145.99  4960.8 1139.43  4980.8 1134.88  4989.5 1130.18
  4990.0 1129.68  5006.4 1130.18  5030.0 1134.58  5035.4 1134.11  5054.3 1137.18
  5205.5 1142.64  5221.5 1142.84  5226.9 1139.81  5245.8 1139.43  5251.2 1143.38
  5259.2 1144.13  5269.9 1142.79  5275.5 1145.23  5280.9 1145.79  5366.8 1151.77
  5413.1 1157.18  5599.3 1190.06  5629.0 1193.65  5635.8 1196.10  5668.1 1202.07
#Mann=5,-1,0
  4720.8    0.05       0  4782.7    0.12       0  4989.5    0.07       0
  5006.4    0.12       0  5205.5    0.05       0
Bank Sta=4989.5,5006.4
Exp/Cntr=0.3,0.1

Type RM Length L Ch R = 1,47033,493,493,493
BEGIN DESCRIPTION:
WRIGHTS CREEK 80.0
END DESCRIPTION:
XS GIS Cut Line= 3
      2819805.69     10268353.11      2819291.00     10268135.00
      2819005.67     10268153.11
#Sta/Elev= 30
  4441.0 1179.78  4484.7 1173.88  4508.3 1172.84  4538.8 1167.10  4549.6 1166.40
  4580.7 1161.85  4603.0 1159.82  4608.5 1158.56  4625.6 1158.64  4701.7 1151.59
  4732.3 1146.75  4756.0 1141.56  4785.1 1138.16  4837.8 1134.22  4890.6 1133.23
  4914.3 1131.62  4967.1 1131.48  4987.5 1129.31  4988.0 1128.81  5004.5 1129.31
  5005.3 1130.17  5025.4 1135.93  5055.4 1140.16  5115.8 1145.63  5205.5 1163.36
  5208.9 1163.39  5215.7 1166.53  5235.8 1172.66  5255.8 1175.50  5285.9 1181.87
#Mann=7,-1,0
  4441.0    0.05       0  4580.7    0.12       0  4756.0    0.05       0
  4987.5    0.05       0  5004.5    0.05       0  5115.8    0.12       0
  5205.5    0.05       0
Bank Sta=4987.5,5004.5
Exp/Cntr=0.3,0.1

Type RM Length L Ch R = 1,46540,438,438,438
BEGIN DESCRIPTION:
WRIGHTS CREEK 79.0
END DESCRIPTION:
XS GIS Cut Line= 3
      2819705.68     10267853.11      2819352.25     10267688.00
      2819105.71     10267653.11
#Sta/Elev= 30
  4609.9 1165.99  4646.2 1161.85  4669.8 1159.61  4692.6 1156.45  4698.2 1154.77
  4709.2 1154.59  4715.5 1152.65  4797.5 1143.49  4819.6 1143.04  4876.2 1138.63
  4946.4 1133.18  4963.7 1131.29  4972.4 1129.91  4976.7 1126.88  4977.2 1126.38
  4993.7 1126.88  5016.7 1127.60  5036.9 1133.28  5047.0 1138.51  5057.1 1145.83
  5066.4 1150.90  5117.7 1159.37  5137.4 1164.04  5142.5 1163.94  5148.0 1167.29
  5164.6 1171.84  5198.5 1178.02  5208.5 1178.31  5213.5 1177.25  5249.0 1185.29
#Mann=8,-1,0
  4609.9    0.05       0  4646.2    0.12       0  4876.2    0.05       0
  4946.4    0.12       0  4963.7    0.05       0  4976.7    0.05       0
  4993.7    0.05       0  5164.6    0.12       0
Bank Sta=4976.7,4993.7
Exp/Cntr=0.3,0.1

Type RM Length L Ch R = 1,46102,475,475,475
BEGIN DESCRIPTION:
WRIGHTS CREEK 78.0
END DESCRIPTION:
XS GIS Cut Line= 3
      2819755.69     10267703.13      2819641.50     10267367.00
      2819655.69     10267153.07
#Sta/Elev= 30
  4645.0 1156.94  4660.7 1155.35  4666.1 1153.98  4676.7 1152.75  4692.1 1151.53
  4697.8 1150.22  4723.5 1147.91  4761.2 1142.79  4771.8 1142.54  4786.3 1140.61
  4831.1 1137.67  4843.8 1136.53  4849.0 1136.75  4898.5 1134.44  4961.9 1130.09
  4969.3 1128.89  4990.9 1123.40  4991.4 1122.90  5007.4 1122.90  5007.9 1123.40
  5034.0 1130.58  5044.0 1137.23  5054.0 1142.22  5110.8 1152.80  5134.0 1158.10
  5139.0 1158.64  5144.2 1160.66  5184.3 1169.86  5211.9 1177.79  5214.4 1177.79
#Mann=5,-1,0
  4645.0    0.12       0  4831.1    0.05       0  4990.9    0.05       0
  5007.9    0.05       0  5110.8    0.12       0
Bank Sta=4990.9,5007.9
Exp/Cntr=0.3,0.1

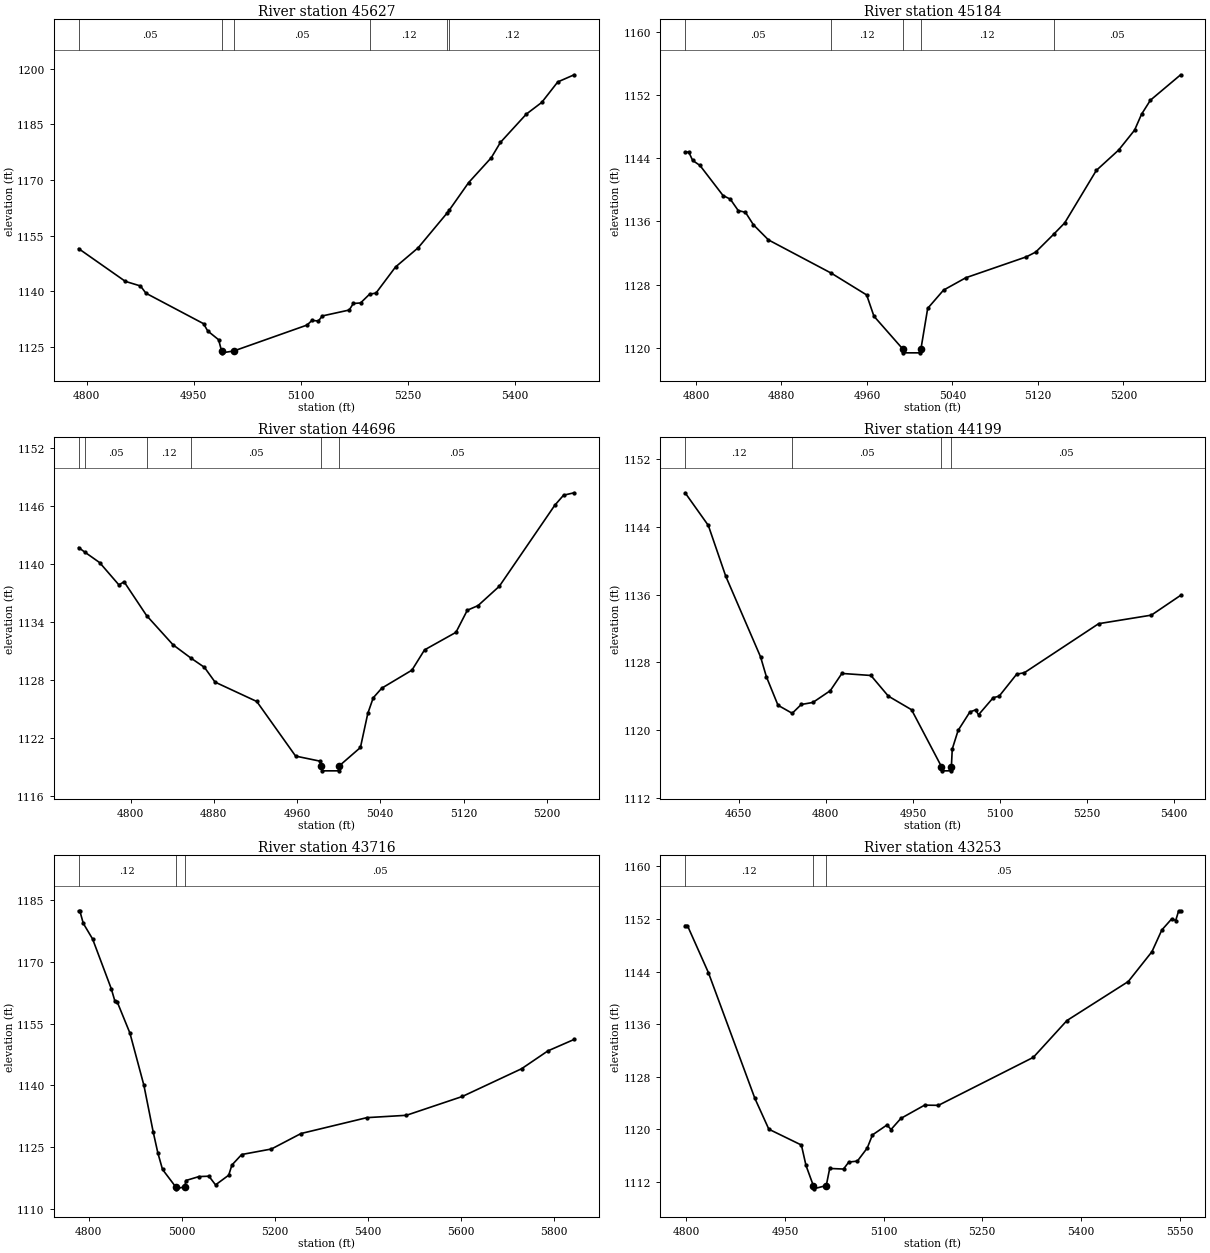
Type RM Length L Ch R = 1,45627,443,443,443
BEGIN DESCRIPTION:
WRIGHTS CREEK 77.0
END DESCRIPTION:
XS GIS Cut Line= 3
      2820255.71     10267303.13      2820076.50     10267191.00
      2819655.69     10266953.11
#Sta/Elev= 30
  4788.6 1151.49  4854.1 1142.66  4875.3 1141.42  4883.0 1139.46  4963.7 1131.25
  4969.6 1129.28  4984.9 1126.91  4989.0 1123.88  4989.5 1123.38  5006.1 1123.88
  5108.8 1130.87  5115.8 1132.13  5124.7 1131.97  5130.4 1133.34  5168.0 1134.93
  5173.7 1136.69  5183.9 1136.84  5196.6 1139.21  5205.5 1139.50  5232.9 1146.54
  5264.7 1151.73  5305.6 1161.18  5308.2 1161.86  5335.4 1169.30  5367.2 1176.02
  5380.0 1180.15  5416.3 1187.78  5437.9 1190.93  5460.4 1196.46  5483.4 1198.39
#Mann=6,-1,0
  4788.6    0.05       0  4989.0    0.05       0  5006.1    0.05       0
  5196.6    0.12       0  5305.6    0.05       0  5308.2    0.12       0
Bank Sta=4989,5006.1
Exp/Cntr=0.3,0.1

Type RM Length L Ch R = 1,45184,488,488,488
BEGIN DESCRIPTION:
WRIGHTS CREEK 76.0
END DESCRIPTION:
XS GIS Cut Line= 3
      2820555.72     10267053.14      2820401.00     10266911.00
      2820255.71     10266703.15
#Sta/Elev= 30
  4789.9 1144.79  4793.3 1144.79  4797.0 1143.72  4803.8 1143.09  4825.4 1139.28
  4832.2 1138.82  4839.6 1137.38  4846.4 1137.15  4853.8 1135.58  4867.9 1133.66
  4926.8 1129.44  4959.8 1126.69  4966.6 1124.00  4993.5 1119.86  4994.0 1119.36
  5010.1 1119.36  5010.6 1119.86  5016.9 1124.99  5031.7 1127.30  5052.6 1128.87
  5109.3 1131.52  5118.0 1132.12  5134.9 1134.39  5145.1 1135.81  5174.7 1142.46
  5195.6 1145.04  5210.5 1147.56  5217.0 1149.57  5225.3 1151.35  5253.6 1154.57
#Mann=5,-1,0
  4789.9    0.05       0  4926.8    0.12       0  4993.5    0.07       0
  5010.6    0.12       0  5134.9    0.05       0
Bank Sta=4993.5,5010.6
Exp/Cntr=0.3,0.1

Type RM Length L Ch R = 1,44696,497,497,497
BEGIN DESCRIPTION:
WRIGHTS CREEK 75.0
END DESCRIPTION:
XS GIS Cut Line= 3
      2820805.69     10266853.13      2820776.00     10266605.00
      2820555.73     10266553.12
#Sta/Elev= 30
  4750.1 1141.72  4756.0 1141.25  4770.3 1140.16  4788.8 1137.85  4793.8 1138.17
  4815.4 1134.67  4840.8 1131.64  4857.9 1130.27  4871.0 1129.30  4881.2 1127.77
  4921.3 1125.76  4958.6 1120.10  4981.8 1119.58  4983.3 1119.07  4983.8 1118.57
  4999.9 1118.57  5000.4 1119.07  5020.9 1120.99  5028.0 1124.53  5033.2 1126.14
  5041.4 1127.14  5070.4 1129.01  5082.5 1131.11  5112.7 1132.93  5123.6 1135.22
  5133.9 1135.70  5154.4 1137.71  5207.7 1146.11  5216.1 1147.15  5226.3 1147.40
#Mann=6,-1,0
  4750.1    0.12       0  4756.0    0.05       0  4815.4    0.12       0
  4857.9    0.05       0  4983.3    0.05       0  5000.4    0.05       0
Bank Sta=4983.3,5000.4
Exp/Cntr=0.3,0.1

Type RM Length L Ch R = 1,44199,483,483,483
BEGIN DESCRIPTION:
WRIGHTS CREEK 74.0
END DESCRIPTION:
XS GIS Cut Line= 3
      2821605.64     10266303.11      2821163.25     10266300.00
      2820755.70     10266353.11
#Sta/Elev= 30
  4557.6 1148.05  4597.6 1144.19  4627.6 1138.19  4687.6 1128.65  4697.6 1126.31
  4717.6 1122.94  4742.1 1121.99  4757.6 1123.03  4777.6 1123.27  4807.6 1124.66
  4827.6 1126.70  4877.6 1126.46  4907.6 1124.02  4947.6 1122.41  4999.1 1115.69
  4999.6 1115.19  5015.7 1115.19  5016.2 1115.69  5017.7 1117.77  5027.8 1119.97
  5048.0 1122.14  5057.9 1122.40  5062.9 1121.81  5088.3 1123.84  5098.4 1124.01
  5128.6 1126.61  5142.0 1126.79  5269.8 1132.58  5360.6 1133.59  5411.0 1135.93
#Mann=4,-1,0
  4557.6    0.12       0  4742.1    0.05       0  4999.1    0.05       0
  5016.2    0.05       0
Bank Sta=4999.1,5016.2
Exp/Cntr=0.3,0.1

Type RM Length L Ch R = 1,43716,463,463,463
BEGIN DESCRIPTION:
WRIGHTS CREEK 73.0
END DESCRIPTION:
XS GIS Cut Line= 3
      2821105.69     10265703.13      2821119.50     10265924.00
      2820505.67     10266503.12
#Sta/Elev= 30
  4778.7 1182.44  4781.2 1182.44  4788.7 1179.38  4808.7 1175.59  4848.8 1163.52
  4856.3 1160.63  4861.3 1160.39  4888.9 1152.73  4919.0 1140.03  4939.0 1128.69
  4949.0 1123.59  4959.0 1119.59  4987.2 1115.37  4987.7 1114.87  5006.9 1115.37
  5009.1 1116.89  5037.4 1117.85  5058.8 1117.94  5073.0 1115.83  5101.3 1118.19
  5108.2 1120.66  5129.2 1123.21  5193.1 1124.55  5256.7 1128.31  5398.3 1132.17
  5483.2 1132.74  5603.4 1137.31  5730.8 1144.05  5787.4 1148.39  5843.9 1151.18
#Mann=3,-1,0
  4778.7    0.12       0  4987.2    0.05       0  5006.9    0.05       0
Bank Sta=4987.2,5006.9
Exp/Cntr=0.3,0.1

Type RM Length L Ch R = 1,43253,470,470,470
BEGIN DESCRIPTION:
WRIGHTS CREEK 72.0
END DESCRIPTION:
XS GIS Cut Line= 3
      2820805.71     10265753.09      2820661.25     10265894.00
      2820355.69     10266353.11
#Sta/Elev= 30
  4798.2 1151.02  4801.7 1151.02  4833.6 1143.86  4904.3 1124.72  4925.5 1120.04
  4975.0 1117.63  4982.0 1114.52  4993.1 1111.47  4993.6 1110.97  5012.8 1111.47
  5018.0 1114.07  5039.0 1113.98  5047.0 1115.04  5060.1 1115.19  5075.1 1117.18
  5083.0 1119.17  5105.2 1120.69  5111.2 1119.99  5126.2 1121.68  5162.3 1123.70
  5183.3 1123.67  5327.6 1130.97  5378.7 1136.57  5471.9 1142.50  5507.9 1147.04
  5522.9 1150.34  5538.0 1152.04  5544.0 1151.78  5548.5 1153.26  5551.5 1153.26
#Mann=3,-1,0
  4798.2    0.12       0  4993.1    0.07       0  5012.8    0.05       0
Bank Sta=4993.1,5012.8
Exp/Cntr=0.3,0.1