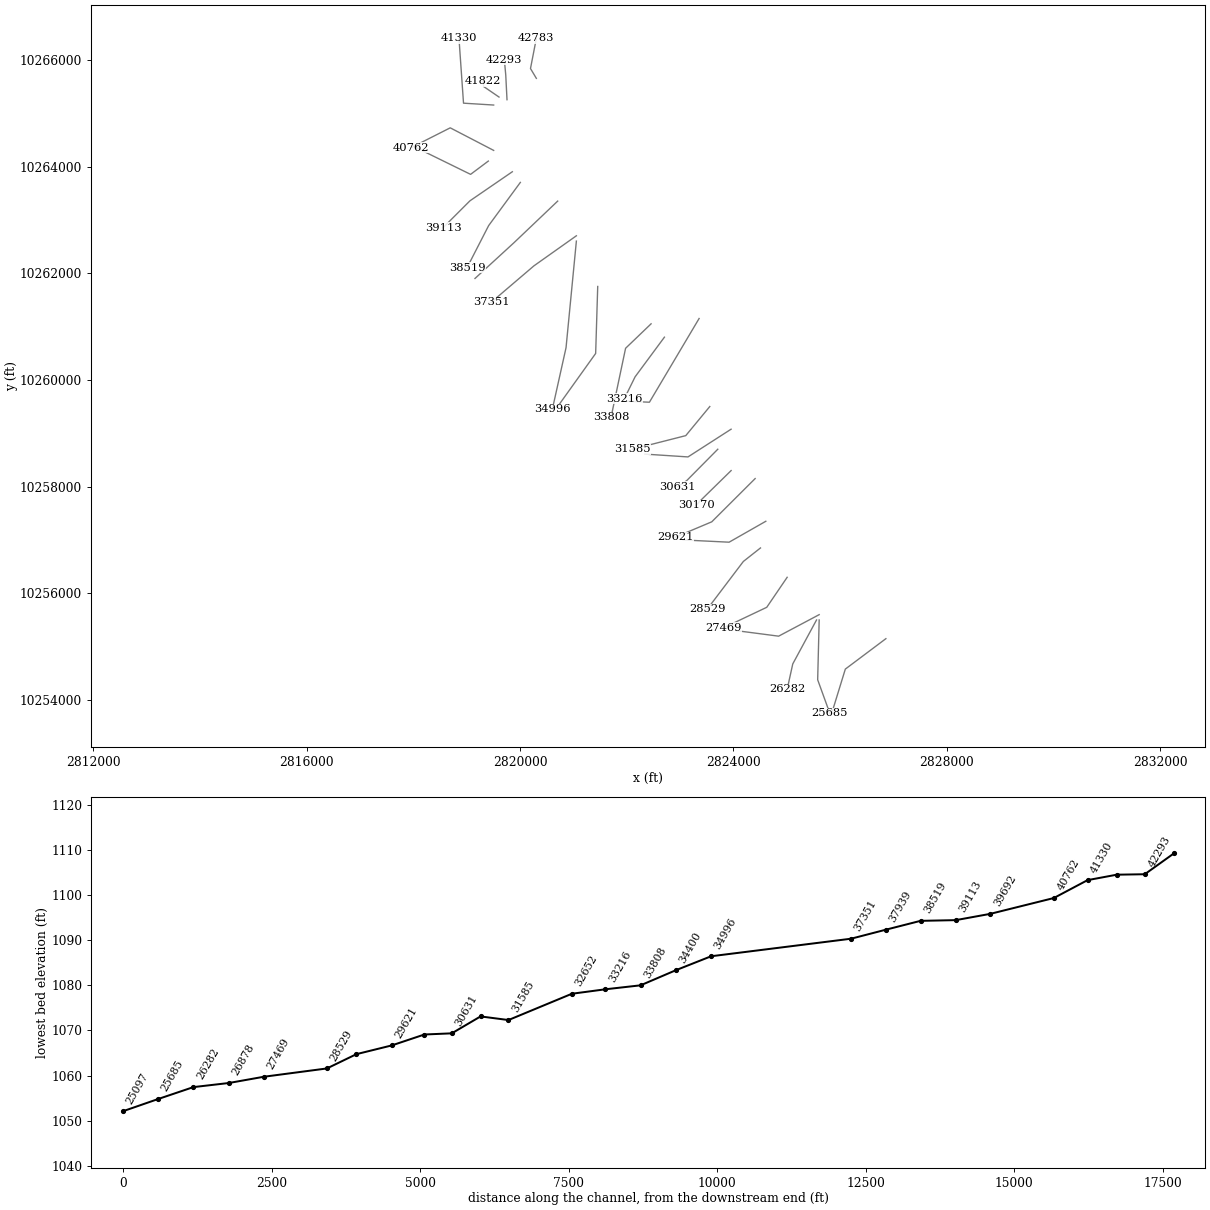
HEC-RAS study WRIGHTS CREEK.prj: WRIGHTS CREEK Base Level Engineering

--- WRIGHTS CREEK.g01 (geometry) --- (continued)

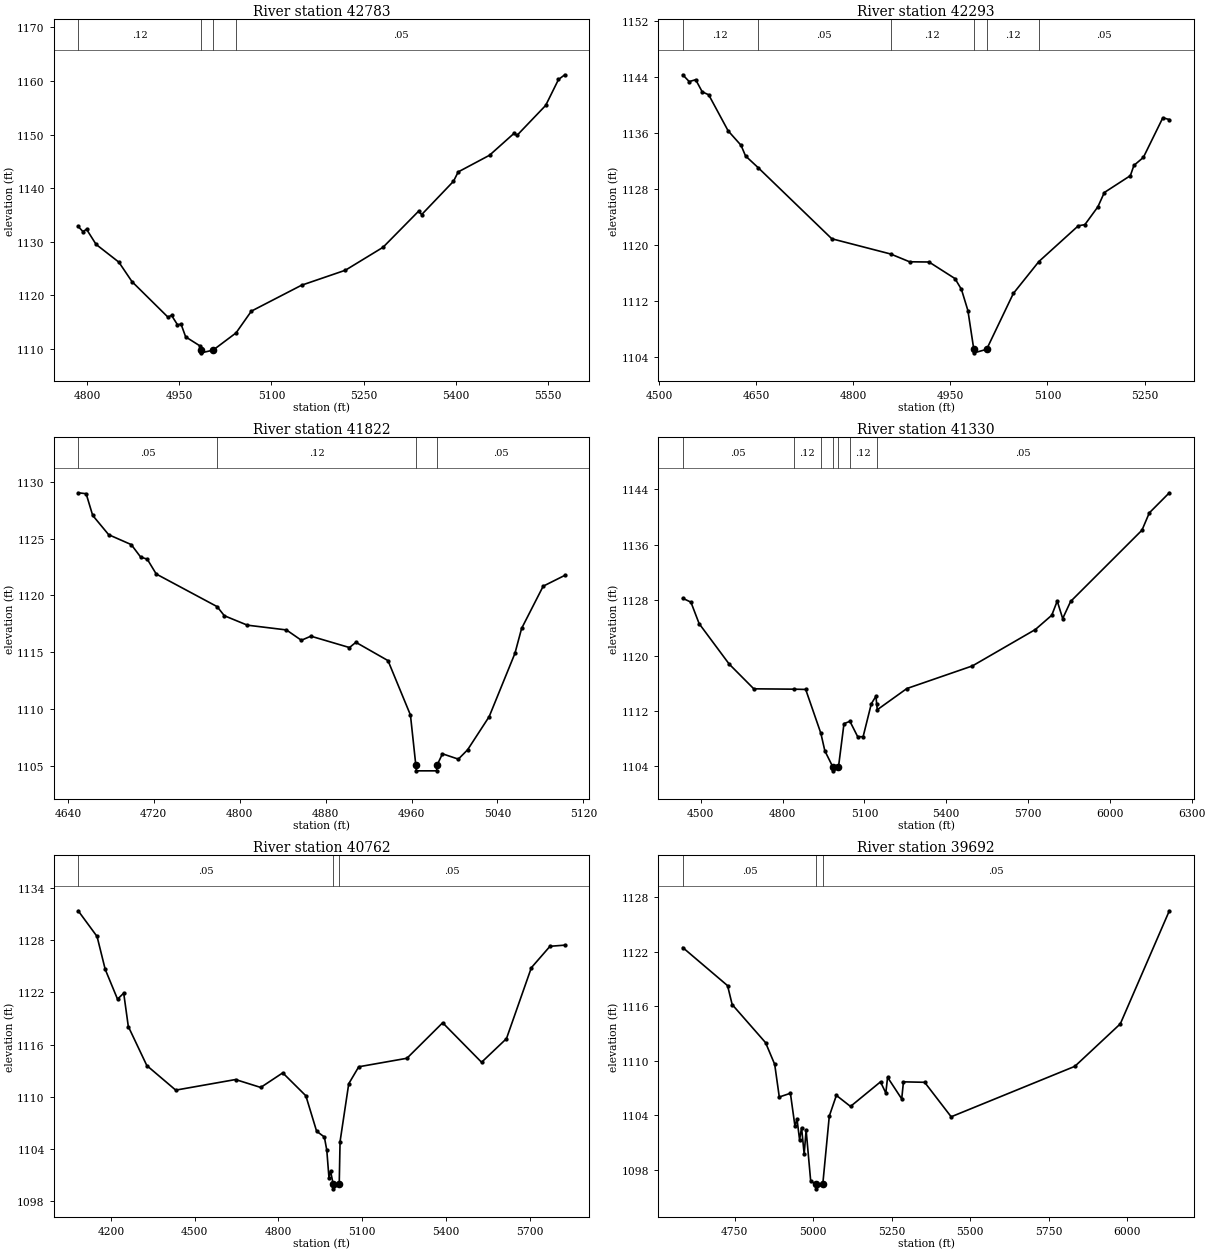
Type RM Length L Ch R = 1,42783,490,490,490
BEGIN DESCRIPTION:
WRIGHTS CREEK 71.0
END DESCRIPTION:
XS GIS Cut Line= 3
      2820305.66     10265653.15      2820195.75     10265837.00
      2820305.69     10266403.12
#Sta/Elev= 30
  4785.8 1132.86  4793.5 1131.90  4799.4 1132.33  4814.9 1129.51  4851.9 1126.20
  4873.3 1122.56  4931.7 1115.94  4937.5 1116.28  4947.2 1114.52  4953.0 1114.63
  4960.5 1112.26  4983.8 1110.57  4985.3 1109.78  4985.8 1109.28  5005.0 1109.78
  5042.4 1113.00  5067.3 1117.06  5148.8 1121.89  5220.1 1124.69  5281.3 1128.97
  5339.0 1135.69  5344.1 1135.07  5395.8 1141.28  5403.5 1143.03  5454.4 1146.14
  5494.1 1150.21  5499.1 1149.85  5545.7 1155.44  5566.5 1160.27  5576.7 1161.15
#Mann=4,-1,0
  4785.8    0.12       0  4985.3    0.07       0  5005.0    0.12       0
  5042.4    0.05       0
Bank Sta=4985.3,5005
Exp/Cntr=0.3,0.1

Type RM Length L Ch R = 1,42293,471,471,471
BEGIN DESCRIPTION:
WRIGHTS CREEK 70.0
END DESCRIPTION:
XS GIS Cut Line= 3
      2819755.69     10265253.09      2819732.25     10265716.00
      2819705.69     10266003.07
#Sta/Elev= 30
  4536.5 1144.27  4546.5 1143.30  4556.5 1143.57  4566.6 1141.84  4576.6 1141.42
  4606.6 1136.29  4626.6 1134.22  4633.5 1132.71  4652.9 1131.05  4766.8 1120.91
  4857.7 1118.74  4887.0 1117.63  4917.0 1117.60  4957.1 1115.24  4967.1 1113.70
  4977.1 1110.68  4986.2 1105.16  4986.7 1104.66  5006.0 1105.16  5047.3 1113.12
  5086.8 1117.67  5147.7 1122.76  5157.8 1122.92  5177.9 1125.46  5187.9 1127.50
  5228.1 1129.90  5233.6 1131.36  5248.2 1132.50  5278.3 1138.15  5288.3 1137.89
#Mann=6,-1,0
  4536.5    0.12       0  4652.9    0.05       0  4857.7    0.12       0
  4986.2    0.07       0  5006.0    0.12       0  5086.8    0.05       0
Bank Sta=4986.2,5006
Exp/Cntr=0.3,0.1

Type RM Length L Ch R = 1,41822,492,492,492
BEGIN DESCRIPTION:
WRIGHTS CREEK 69.0
END DESCRIPTION:
XS GIS Cut Line= 3
      2819605.68     10265303.12      2819316.50     10265501.00
      2819305.68     10265603.13
#Sta/Elev= 30
  4649.6 1129.03  4657.0 1128.95  4663.1 1127.04  4678.0 1125.34  4699.0 1124.47
  4707.8 1123.37  4713.9 1123.19  4722.3 1121.88  4779.0 1119.01  4785.7 1118.21
  4807.1 1117.38  4843.5 1116.96  4857.4 1116.05  4866.3 1116.41  4902.2 1115.41
  4908.2 1115.87  4938.1 1114.26  4959.0 1109.47  4964.0 1105.06  4964.5 1104.56
  4983.3 1104.56  4983.8 1105.06  4988.8 1106.06  5003.6 1105.59  5012.2 1106.41
  5032.3 1109.33  5056.3 1114.90  5062.5 1117.09  5082.6 1120.81  5102.7 1121.76
#Mann=4,-1,0
  4649.6    0.05       0  4779.0    0.12       0  4964.0    0.05       0
  4983.8    0.05       0
Bank Sta=4964,4983.8
Exp/Cntr=0.3,0.1

Type RM Length L Ch R = 1,41330,568,568,568
BEGIN DESCRIPTION:
WRIGHTS CREEK 68.0
END DESCRIPTION:
XS GIS Cut Line= 3
      2819505.67     10265153.11      2818940.75     10265188.00
      2818855.68     10266403.13
#Sta/Elev= 30
  4434.0 1128.26  4464.0 1127.70  4494.1 1124.60  4604.3 1118.76  4694.5 1115.19
  4841.2 1115.14  4884.8 1115.10  4940.5 1108.76  4955.0 1106.24  4985.1 1103.85
  4985.6 1103.35  5004.9 1103.85  5025.2 1110.16  5047.0 1110.50  5075.3 1108.29
  5095.3 1108.27  5125.4 1113.03  5142.3 1114.12  5145.2 1112.99  5147.3 1112.17
  5255.7 1115.23  5496.3 1118.50  5726.9 1123.75  5787.0 1125.81  5807.1 1127.86
  5827.1 1125.33  5856.1 1127.80  6117.8 1138.09  6144.7 1140.59  6218.1 1143.49
#Mann=7,-1,0
  4434.0    0.05       0  4841.2    0.12       0  4940.5    0.05       0
  4985.1    0.05       0  5004.9    0.05       0  5047.0    0.12       0
  5145.2    0.05       0
Bank Sta=4985.1,5004.9
Exp/Cntr=0.3,0.1

Type RM Length L Ch R = 1,40762,1070,1070,1070
BEGIN DESCRIPTION:
WRIGHTS CREEK 67.0
END DESCRIPTION:
XS GIS Cut Line= 3
      2819505.65     10264303.13      2818691.75     10264726.00
      2817955.71     10264353.12
#Sta/Elev= 30
  4082.8 1131.41  4150.4 1128.45  4179.5 1124.67  4223.7 1121.23  4245.8 1121.92
  4262.3 1118.08  4328.6 1113.58  4432.1 1110.75  4646.2 1111.97  4736.4 1111.06
  4815.3 1112.74  4898.0 1110.10  4936.5 1106.02  4964.3 1105.35  4973.0 1103.83
  4980.8 1100.64  4986.4 1101.44  4996.1 1099.88  4996.6 1099.38  5017.5 1099.88
  5020.5 1104.82  5051.6 1111.49  5087.4 1113.44  5259.9 1114.42  5387.9 1118.51
  5527.2 1113.96  5616.3 1116.68  5705.4 1124.85  5772.2 1127.32  5825.1 1127.45
#Mann=3,-1,0
  4082.8    0.05       0  4996.1    0.05       0  5017.5    0.05       0
Bank Sta=4996.1,5017.5
Exp/Cntr=0.3,0.1

Type RM Length L Ch R = 1,39692,579,579,579
BEGIN DESCRIPTION:
WRIGHTS CREEK 65.0
END DESCRIPTION:
XS GIS Cut Line= 3
      2819405.67     10264103.10      2819073.25     10263854.00
      2818055.67     10264353.12
#Sta/Elev= 30
  4584.6 1122.46  4727.3 1118.26  4741.9 1116.18  4848.2 1111.98  4877.3 1109.59
  4891.9 1105.99  4927.3 1106.40  4941.9 1102.74  4948.2 1103.59  4956.5 1101.27
  4962.8 1102.61  4971.1 1099.70  4977.3 1102.34  4991.9 1096.72  5008.8 1096.37
  5009.3 1095.87  5030.3 1096.37  5051.1 1103.89  5073.6 1106.17  5118.6 1104.95
  5214.1 1107.66  5231.0 1106.43  5236.6 1108.16  5281.6 1105.78  5287.1 1107.66
  5354.6 1107.61  5439.0 1103.81  5832.7 1109.37  5977.4 1114.05  6133.4 1126.51
#Mann=3,-1,0
  4584.6    0.05       0  5008.8    0.05       0  5030.3    0.05       0
Bank Sta=5008.8,5030.3
Exp/Cntr=0.3,0.1

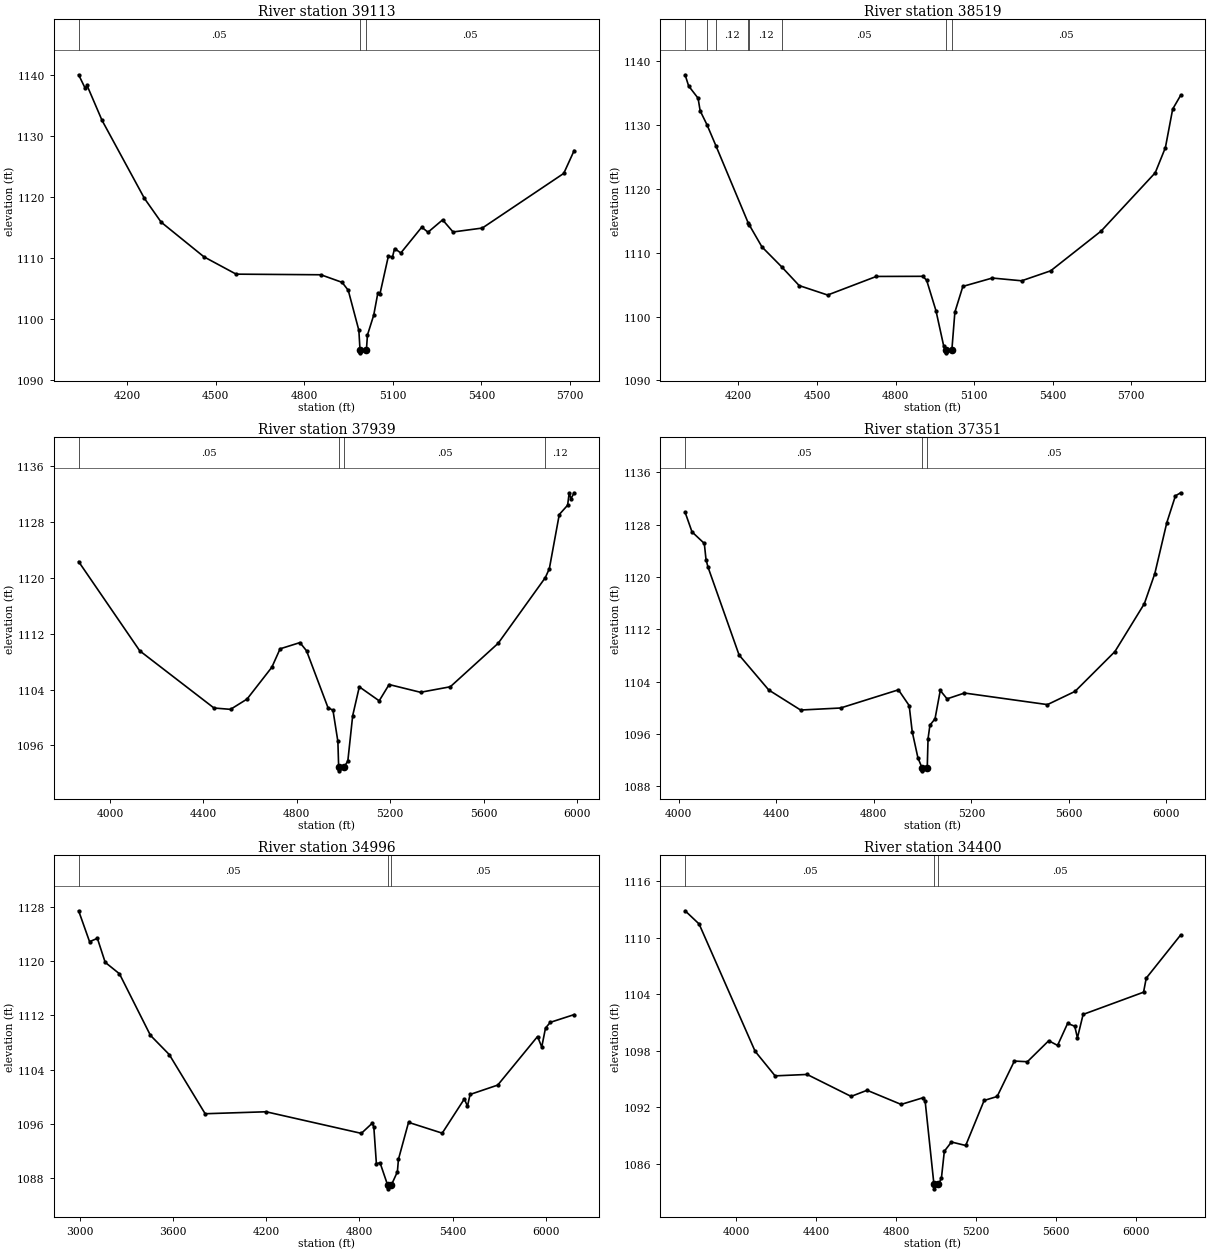
Type RM Length L Ch R = 1,39113,594,594,594
BEGIN DESCRIPTION:
WRIGHTS CREEK 64.0
END DESCRIPTION:
XS GIS Cut Line= 3
      2819855.70     10263903.13      2819061.00     10263358.00
      2818555.70     10262853.13
#Sta/Elev= 30
  4036.3 1139.96  4058.7 1137.73  4064.7 1138.23  4115.5 1132.51  4259.0 1119.75
  4315.8 1115.85  4460.8 1110.18  4569.7 1107.35  4856.6 1107.25  4928.4 1106.01
  4949.3 1104.71  4985.2 1098.16  4989.1 1094.98  4989.6 1094.48  5010.8 1094.98
  5014.3 1097.39  5035.5 1100.64  5049.6 1104.29  5056.7 1104.13  5085.0 1110.27
  5099.1 1110.18  5106.2 1111.53  5127.4 1110.82  5198.1 1115.03  5219.4 1114.21
  5268.8 1116.23  5304.2 1114.25  5403.2 1114.89  5679.0 1123.83  5714.3 1127.57
#Mann=3,-1,0
  4036.3    0.05       0  4989.1    0.05       0  5010.8    0.05       0
Bank Sta=4989.1,5010.8
Exp/Cntr=0.3,0.1

Type RM Length L Ch R = 1,38519,580,580,580
BEGIN DESCRIPTION:
WRIGHTS CREEK 63.0
END DESCRIPTION:
XS GIS Cut Line= 3
      2820005.68     10263703.11      2819411.75     10262894.00
      2819005.70     10262103.15
#Sta/Elev= 30
  3996.3 1137.85  4009.8 1136.10  4045.9 1134.18  4053.8 1132.21  4080.2 1130.00
  4114.7 1126.67  4237.8 1114.61  4240.6 1114.40  4289.9 1110.90  4366.4 1107.73
  4432.0 1104.85  4540.7 1103.37  4726.7 1106.28  4904.2 1106.30  4918.9 1105.68
  4954.4 1100.93  4983.7 1095.45  4993.6 1094.82  4994.1 1094.32  5015.3 1094.82
  5026.7 1100.69  5057.2 1104.72  5169.6 1106.03  5281.7 1105.60  5392.6 1107.16
  5585.5 1113.39  5792.0 1122.51  5830.8 1126.45  5858.6 1132.48  5889.0 1134.63
#Mann=8,-1,0
  3996.3    0.12       0  4080.2    0.05       0  4114.7    0.12       0
  4237.8    0.05       0  4240.6    0.12       0  4366.4    0.05       0
  4993.6    0.05       0  5015.3    0.05       0
Bank Sta=4993.6,5015.3
Exp/Cntr=0.3,0.1

Type RM Length L Ch R = 1,37939,588,588,588
BEGIN DESCRIPTION:
WRIGHTS CREEK 62.0
END DESCRIPTION:
XS GIS Cut Line= 3
      2820705.68     10263353.11      2819884.00     10262571.00
      2819155.68     10261903.10
#Sta/Elev= 30
  3865.6 1122.31  4127.5 1109.54  4445.4 1101.36  4516.2 1101.17  4587.0 1102.64
  4693.3 1107.20  4728.5 1109.83  4813.5 1110.72  4841.8 1109.55  4933.6 1101.42
  4955.0 1101.04  4976.1 1096.57  4979.4 1092.87  4979.9 1092.37  5001.1 1092.87
  5018.6 1093.75  5039.5 1100.27  5067.9 1104.39  5153.0 1102.39  5195.5 1104.72
  5330.0 1103.61  5457.6 1104.40  5662.6 1110.62  5864.4 1120.01  5881.8 1121.29
  5924.4 1129.05  5960.1 1130.38  5966.9 1132.14  5974.3 1131.31  5988.2 1132.16
#Mann=4,-1,0
  3865.6    0.05       0  4979.4    0.03       0  5001.1    0.05       0
  5864.4    0.12       0
Bank Sta=4979.4,5001.1
Exp/Cntr=0.3,0.1

Type RM Length L Ch R = 1,37351,2355,2355,2355
BEGIN DESCRIPTION:
WRIGHTS CREEK 61.0
END DESCRIPTION:
XS GIS Cut Line= 3
      2821055.71     10262703.13      2820260.75     10262140.00
      2819455.67     10261453.10
#Sta/Elev= 30
  4025.8 1129.91  4054.1 1126.91  4104.6 1125.14  4111.6 1122.68  4119.4 1121.56
  4247.3 1108.07  4369.1 1102.72  4499.6 1099.66  4663.2 1099.97  4900.8 1102.75
  4944.9 1100.34  4957.3 1096.36  4980.8 1092.34  4997.2 1090.86  4997.7 1090.36
  5019.0 1090.86  5022.3 1095.29  5030.0 1097.34  5050.9 1098.32  5072.4 1102.65
  5100.3 1101.37  5171.7 1102.26  5512.0 1100.49  5625.1 1102.51  5788.7 1108.60
  5909.5 1115.93  5952.3 1120.52  6001.7 1128.34  6036.9 1132.42  6058.3 1132.89
#Mann=3,-1,0
  4025.8    0.05       0  4997.2    0.03       0  5019.0    0.05       0
Bank Sta=4997.2,5019
Exp/Cntr=0.3,0.1

Type RM Length L Ch R = 1,34996,596,596,596
BEGIN DESCRIPTION:
WRIGHTS CREEK 60.0
END DESCRIPTION:
XS GIS Cut Line= 3
      2821055.69     10262603.13      2820862.00     10260606.00
      2820605.69     10259453.15
#Sta/Elev= 30
  2993.5 1127.42  3063.8 1122.87  3114.1 1123.36  3164.3 1119.83  3256.1 1118.14
  3455.2 1109.08  3576.2 1106.25  3807.3 1097.53  4199.1 1097.82  4812.0 1094.64
  4882.3 1096.14  4892.4 1095.55  4908.7 1090.20  4932.6 1090.29  4981.9 1086.97
  4982.4 1086.47  5003.9 1086.97  5043.9 1088.98  5050.6 1090.81  5115.6 1096.26
  5332.2 1094.67  5474.2 1099.70  5494.7 1098.65  5511.5 1100.37  5689.3 1101.75
  5945.4 1108.90  5972.4 1107.36  5996.6 1110.15  6027.4 1110.99  6181.0 1112.13
#Mann=3,-1,0
  2993.5    0.05       0  4981.9    0.03       0  5003.9    0.05       0
Bank Sta=4981.9,5003.9
Exp/Cntr=0.3,0.1

Type RM Length L Ch R = 1,34400,592,592,592
BEGIN DESCRIPTION:
WRIGHTS CREEK 59.0
END DESCRIPTION:
XS GIS Cut Line= 3
      2821455.68     10261753.10      2821417.00     10260498.00
      2820705.69     10259503.13
#Sta/Elev= 30
  3744.3 1112.87  3814.3 1111.47  4094.5 1097.96  4194.5 1095.35  4354.6 1095.50
  4574.7 1093.17  4654.7 1093.82  4824.8 1092.32  4934.9 1093.03  4944.9 1092.69
  4988.9 1083.86  4989.4 1083.36  5011.0 1083.86  5026.3 1084.47  5041.0 1087.35
  5076.6 1088.33  5147.9 1087.96  5240.1 1092.74  5305.2 1093.16  5391.2 1096.92
  5456.3 1096.85  5563.2 1099.08  5607.4 1098.58  5657.5 1100.91  5693.4 1100.62
  5706.7 1099.38  5735.2 1101.87  6037.5 1104.23  6050.9 1105.72  6223.0 1110.30
#Mann=3,-1,0
  3744.3    0.05       0  4988.9    0.05       0  5011.0    0.05       0
Bank Sta=4988.9,5011
Exp/Cntr=0.3,0.1

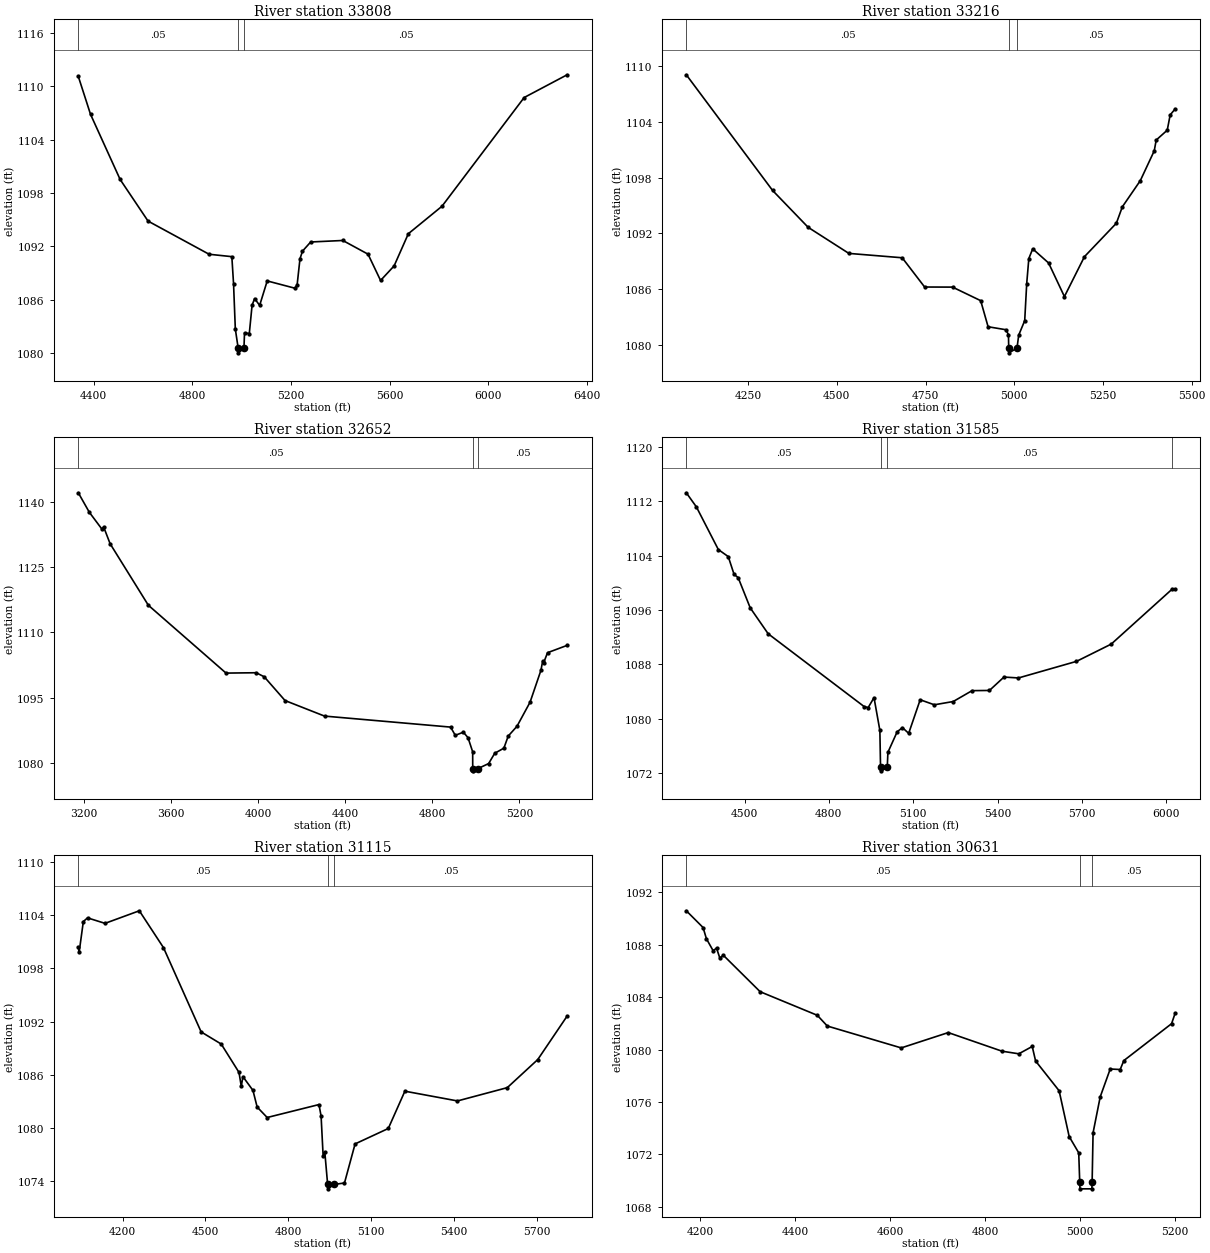
Type RM Length L Ch R = 1,33808,592,592,592
BEGIN DESCRIPTION:
WRIGHTS CREEK 58.0
END DESCRIPTION:
XS GIS Cut Line= 3
      2822455.72     10261053.14      2821978.00     10260595.00
      2821705.68     10259303.09
#Sta/Elev= 30
  4338.1 1111.12  4387.7 1106.85  4507.8 1099.52  4621.0 1094.84  4868.5 1091.11
  4960.7 1090.84  4967.6 1087.81  4974.8 1082.71  4986.5 1080.52  4987.0 1080.02
  5009.8 1080.52  5012.1 1082.27  5031.5 1082.19  5042.8 1085.38  5053.0 1086.12
  5073.5 1085.36  5104.1 1088.11  5216.5 1087.29  5225.5 1087.68  5237.0 1090.60
  5247.2 1091.46  5280.4 1092.49  5410.7 1092.66  5512.9 1091.12  5563.8 1088.16
  5618.7 1089.80  5676.4 1093.42  5812.8 1096.51  6146.0 1108.74  6320.3 1111.30
#Mann=3,-1,0
  4338.1    0.05       0  4986.5    0.05       0  5009.8    0.05       0
Bank Sta=4986.5,5009.8
Exp/Cntr=0.3,0.1

Type RM Length L Ch R = 1,33216,564,564,564
BEGIN DESCRIPTION:
WRIGHTS CREEK 57.0
END DESCRIPTION:
XS GIS Cut Line= 3
      2822705.67     10260803.10      2822156.00     10260060.00
      2821955.70     10259653.13
#Sta/Elev= 30
  4075.7 1109.09  4318.9 1096.63  4419.1 1092.66  4533.9 1089.85  4684.2 1089.38
  4747.4 1086.23  4826.1 1086.22  4905.4 1084.76  4926.3 1081.95  4976.4 1081.63
  4983.7 1081.10  4984.4 1079.64  4984.9 1079.14  5007.7 1079.64  5012.6 1081.05
  5029.5 1082.61  5035.1 1086.59  5041.1 1089.30  5052.0 1090.34  5096.8 1088.82
  5141.4 1085.20  5197.9 1089.50  5287.8 1093.10  5304.7 1094.87  5355.2 1097.68
  5394.6 1100.90  5400.1 1102.06  5431.2 1103.12  5439.5 1104.77  5453.5 1105.41
#Mann=3,-1,0
  4075.7    0.05       0  4984.4    0.03       0  5007.7    0.05       0
Bank Sta=4984.4,5007.7
Exp/Cntr=0.3,0.1

Type RM Length L Ch R = 1,32652,1067,1067,1067
BEGIN DESCRIPTION:
WRIGHTS CREEK 56.0
END DESCRIPTION:
XS GIS Cut Line= 3
      2823355.68     10261153.10      2822424.50     10259584.00
      2822005.64     10259603.11
#Sta/Elev= 30
  3175.4 1142.04  3226.0 1137.56  3284.5 1133.65  3291.7 1134.20  3321.5 1130.33
  3496.9 1116.20  3853.5 1100.61  3991.9 1100.69  4028.9 1099.76  4124.4 1094.30
  4305.6 1090.73  4884.4 1088.20  4905.8 1086.31  4942.9 1087.03  4964.3 1085.77
  4985.7 1082.52  4985.9 1078.65  4986.4 1078.15  5009.3 1078.65  5058.9 1079.82
  5087.0 1082.19  5128.9 1083.36  5149.0 1086.15  5189.0 1088.38  5249.1 1093.92
  5299.1 1101.26  5306.8 1103.34  5311.9 1103.03  5329.2 1105.29  5419.3 1106.98
#Mann=3,-1,0
  3175.4    0.05       0  4985.9    0.05       0  5009.3    0.05       0
Bank Sta=4985.9,5009.3
Exp/Cntr=0.3,0.1

Type RM Length L Ch R = 1,31585,470,470,470
BEGIN DESCRIPTION:
WRIGHTS CREEK 54.0
END DESCRIPTION:
XS GIS Cut Line= 3
      2823555.70     10259503.13      2823105.50     10258958.00
      2822105.68     10258703.11
#Sta/Elev= 30
  4293.0 1113.24  4328.9 1111.16  4407.0 1104.88  4442.2 1103.85  4463.0 1101.22
  4477.4 1100.76  4520.4 1096.30  4584.2 1092.49  4925.5 1081.78  4939.9 1081.63
  4960.7 1083.09  4981.5 1078.27  4983.9 1072.82  4984.4 1072.32  5007.8 1072.82
  5010.1 1075.05  5043.1 1078.07  5061.7 1078.68  5084.0 1077.84  5124.9 1082.78
  5175.2 1082.04  5242.4 1082.52  5309.4 1084.12  5371.3 1084.15  5422.9 1086.12
  5474.5 1085.99  5680.9 1088.43  5804.4 1090.97  6022.2 1099.10  6031.8 1099.02
#Mann=4,-1,0
  4293.0    0.05       0  4983.9    0.03       0  5007.8    0.05       0
  6022.2    0.12       0
Bank Sta=4983.9,5007.8
Exp/Cntr=0.3,0.1

Type RM Length L Ch R = 1,31115,484,484,484
BEGIN DESCRIPTION:
WRIGHTS CREEK 53.0
END DESCRIPTION:
XS GIS Cut Line= 3
      2823955.11     10259078.55      2823147.25     10258559.00
      2822339.48     10258611.88
#Sta/Elev= 30
  4039.5 1100.41  4042.5 1099.80  4057.7 1103.28  4072.9 1103.70  4136.3 1103.08
  4260.5 1104.50  4347.9 1100.34  4484.3 1090.83  4557.0 1089.46  4621.4 1086.26
  4629.6 1084.69  4635.6 1085.78  4671.9 1084.23  4687.1 1082.35  4723.4 1081.17
  4910.9 1082.63  4918.6 1081.34  4926.1 1076.78  4932.1 1077.26  4942.3 1073.62
  4942.8 1073.12  4966.3 1073.62  5003.3 1073.78  5041.7 1078.19  5161.9 1079.93
  5222.0 1084.14  5412.4 1083.04  5592.8 1084.54  5703.1 1087.71  5809.5 1092.62
#Mann=3,-1,0
  4039.5    0.05       0  4942.3    0.03       0  4966.3    0.05       0
Bank Sta=4942.3,4966.3
Exp/Cntr=0.3,0.1

Type RM Length L Ch R = 1,30631,461,461,461
BEGIN DESCRIPTION:
WRIGHTS CREEK 52.0
END DESCRIPTION:
XS GIS Cut Line= 3
      2823705.67     10258703.09      2823122.25     10258114.00
      2822955.69     10258003.11
#Sta/Elev= 30
  4170.9 1090.60  4206.2 1089.32  4213.3 1088.46  4227.4 1087.55  4234.5 1087.75
  4241.6 1086.98  4248.7 1087.21  4326.4 1084.42  4446.7 1082.62  4467.8 1081.80
  4623.4 1080.13  4722.4 1081.30  4835.5 1079.88  4870.9 1079.68  4899.2 1080.24
  4906.3 1079.13  4955.8 1076.86  4977.0 1073.36  4997.1 1072.12  4999.2 1069.87
  4999.7 1069.37  5024.8 1069.37  5025.3 1069.87  5027.3 1073.65  5042.3 1076.39
  5063.4 1078.52  5084.4 1078.48  5092.0 1079.16  5192.6 1081.98  5200.1 1082.78
#Mann=3,-1,0
  4170.9    0.05       0  4999.2    0.03       0  5025.3    0.05       0
Bank Sta=4999.2,5025.3
Exp/Cntr=0.3,0.1

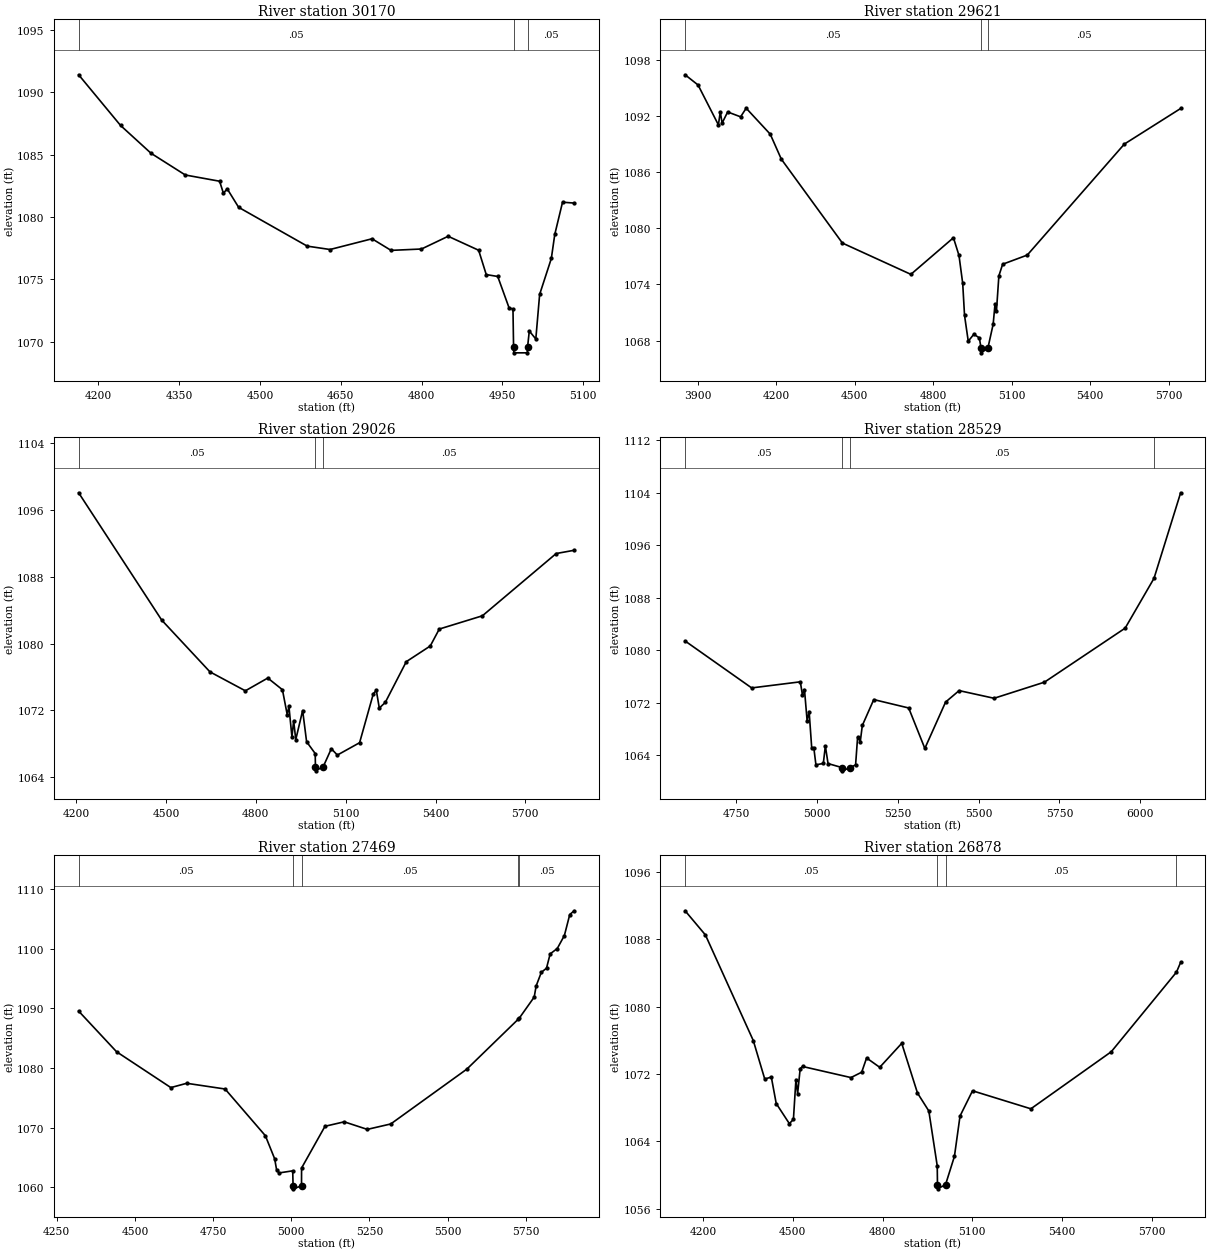
Type RM Length L Ch R = 1,30170,549,549,549
BEGIN DESCRIPTION:
WRIGHTS CREEK 51.0
END DESCRIPTION:
XS GIS Cut Line= 3
      2823955.69     10258303.12      2823357.75     10257718.00
      2823305.68     10257653.11
#Sta/Elev= 30
  4163.4 1091.39  4241.2 1087.33  4297.8 1085.10  4361.4 1083.36  4425.1 1082.86
  4432.1 1081.90  4439.2 1082.25  4460.4 1080.77  4587.7 1077.66  4630.1 1077.39
  4708.0 1078.25  4743.3 1077.32  4799.8 1077.43  4849.3 1078.45  4905.9 1077.33
  4920.0 1075.38  4941.3 1075.23  4962.4 1072.71  4969.6 1072.62  4970.7 1069.61
  4971.2 1069.11  4996.3 1069.11  4996.8 1069.61  4999.9 1070.86  5012.0 1070.22
  5019.1 1073.79  5040.8 1076.67  5047.2 1078.60  5061.6 1081.18  5083.2 1081.11
#Mann=3,-1,0
  4163.4    0.05       0  4970.7    0.05       0  4996.8    0.05       0
Bank Sta=4970.7,4996.8
Exp/Cntr=0.3,0.1

Type RM Length L Ch R = 1,29621,595,595,595
BEGIN DESCRIPTION:
WRIGHTS CREEK 50.0
END DESCRIPTION:
XS GIS Cut Line= 3
      2824405.69     10258153.12      2823593.00     10257343.00
      2822905.73     10257053.13
#Sta/Elev= 30
  3852.5 1096.38  3902.0 1095.29  3979.8 1091.03  3986.9 1092.43  3993.9 1091.22
  4015.1 1092.41  4064.6 1091.89  4085.9 1092.81  4177.8 1090.04  4220.2 1087.37
  4453.6 1078.41  4715.2 1075.07  4877.8 1078.98  4899.0 1077.09  4913.2 1074.11
  4920.2 1070.68  4934.4 1067.93  4955.6 1068.67  4976.8 1068.29  4983.3 1067.19
  4983.8 1066.69  5009.4 1067.19  5029.6 1069.75  5036.7 1071.91  5042.1 1071.13
  5051.4 1074.91  5065.8 1076.15  5159.9 1077.13  5530.8 1088.98  5745.9 1092.78
#Mann=3,-1,0
  3852.5    0.05       0  4983.3    0.03       0  5009.4    0.05       0
Bank Sta=4983.3,5009.4
Exp/Cntr=0.3,0.1

Type RM Length L Ch R = 1,29026,497,497,497
BEGIN DESCRIPTION:
WRIGHTS CREEK 49.0
END DESCRIPTION:
XS GIS Cut Line= 3
      2824605.65     10257353.09      2823917.75     10256961.00
      2823055.68     10257003.11
#Sta/Elev= 30
  4208.2 1098.07  4485.5 1082.82  4646.8 1076.61  4765.0 1074.34  4839.9 1075.87
  4888.8 1074.47  4904.7 1071.50  4910.5 1072.46  4920.6 1068.80  4926.3 1070.77
  4933.3 1068.49  4956.3 1071.98  4969.5 1068.24  4998.3 1066.82  4999.0 1065.25
  4999.5 1064.75  5025.1 1065.25  5052.1 1067.40  5072.2 1066.64  5146.5 1068.12
  5192.3 1073.98  5202.3 1074.40  5212.3 1072.27  5232.3 1072.95  5302.4 1077.83
  5382.5 1079.71  5412.6 1081.74  5556.7 1083.33  5803.0 1090.79  5863.1 1091.18
#Mann=3,-1,0
  4208.2    0.05       0  4999.0    0.05       0  5025.1    0.05       0
Bank Sta=4999,5025.1
Exp/Cntr=0.3,0.1

Type RM Length L Ch R = 1,28529,1060,1060,1060
BEGIN DESCRIPTION:
WRIGHTS CREEK 48.0
END DESCRIPTION:
XS GIS Cut Line= 3
      2824505.66     10256853.09      2824184.75     10256600.00
      2823505.66     10255703.08
#Sta/Elev= 30
  4591.3 1081.39  4797.3 1074.23  4947.9 1075.16  4954.4 1073.18  4960.8 1073.97
  4968.9 1069.25  4975.2 1070.62  4983.3 1064.99  4989.7 1065.09  4996.2 1062.50
  5019.1 1062.71  5025.4 1065.38  5033.7 1062.69  5076.7 1062.08  5077.2 1061.58
  5103.0 1062.08  5119.0 1062.50  5125.2 1066.71  5133.5 1066.04  5139.8 1068.50
  5175.2 1072.45  5283.3 1071.17  5333.3 1065.00  5397.5 1072.07  5439.4 1073.82
  5547.6 1072.65  5703.6 1075.11  5953.3 1083.35  6042.6 1090.95  6125.0 1104.00
#Mann=4,-1,0
  4591.3    0.05       0  5076.7    0.03       0  5103.0    0.05       0
  6042.6    0.12       0
Bank Sta=5076.7,5103
Exp/Cntr=0.3,0.1

Type RM Length L Ch R = 1,27469,591,591,591
BEGIN DESCRIPTION:
WRIGHTS CREEK 46.0
END DESCRIPTION:
XS GIS Cut Line= 3
      2825005.70     10256303.14      2824623.25     10255741.00
      2823805.70     10255353.12
#Sta/Elev= 30
  4320.1 1089.55  4441.4 1082.73  4615.0 1076.72  4665.8 1077.44  4788.5 1076.48
  4917.3 1068.65  4947.1 1064.77  4953.2 1062.93  4961.2 1062.41  5004.8 1062.76
  5005.9 1060.24  5006.4 1059.74  5032.9 1060.24  5033.1 1063.23  5108.0 1070.23
  5169.5 1070.98  5243.2 1069.71  5318.3 1070.62  5561.5 1079.81  5725.3 1088.15
  5729.3 1088.36  5777.1 1091.90  5783.2 1093.75  5799.8 1096.04  5816.4 1096.74
  5828.1 1099.14  5850.8 1100.04  5873.6 1102.22  5890.8 1105.74  5904.9 1106.37
#Mann=5,-1,0
  4320.1    0.05       0  5005.9    0.03       0  5032.9    0.05       0
  5725.3    0.12       0  5729.3    0.05       0
Bank Sta=5005.9,5032.9
Exp/Cntr=0.3,0.1

Type RM Length L Ch R = 1,26878,596,596,596
BEGIN DESCRIPTION:
WRIGHTS CREEK 45.0
END DESCRIPTION:
XS GIS Cut Line= 3
      2825605.66     10255603.10      2824845.75     10255200.00
      2824055.65     10255303.12
#Sta/Elev= 30
  4139.8 1091.39  4207.7 1088.52  4367.8 1075.97  4406.1 1071.40  4428.1 1071.63
  4444.5 1068.49  4488.4 1066.10  4502.0 1066.60  4510.4 1071.34  4516.1 1069.67
  4524.6 1072.63  4532.4 1072.89  4694.4 1071.57  4730.3 1072.21  4746.7 1073.90
  4790.6 1072.79  4864.2 1075.64  4916.9 1069.73  4954.8 1067.60  4982.9 1061.08
  4983.7 1058.85  4984.2 1058.35  5010.7 1058.85  5040.4 1062.21  5059.1 1067.00
  5100.9 1070.00  5296.0 1067.86  5564.8 1074.64  5782.9 1084.10  5796.8 1085.26
#Mann=4,-1,0
  4139.8    0.05       0  4983.7    0.03       0  5010.7    0.05       0
  5782.9    0.12       0
Bank Sta=4983.7,5010.7
Exp/Cntr=0.3,0.1

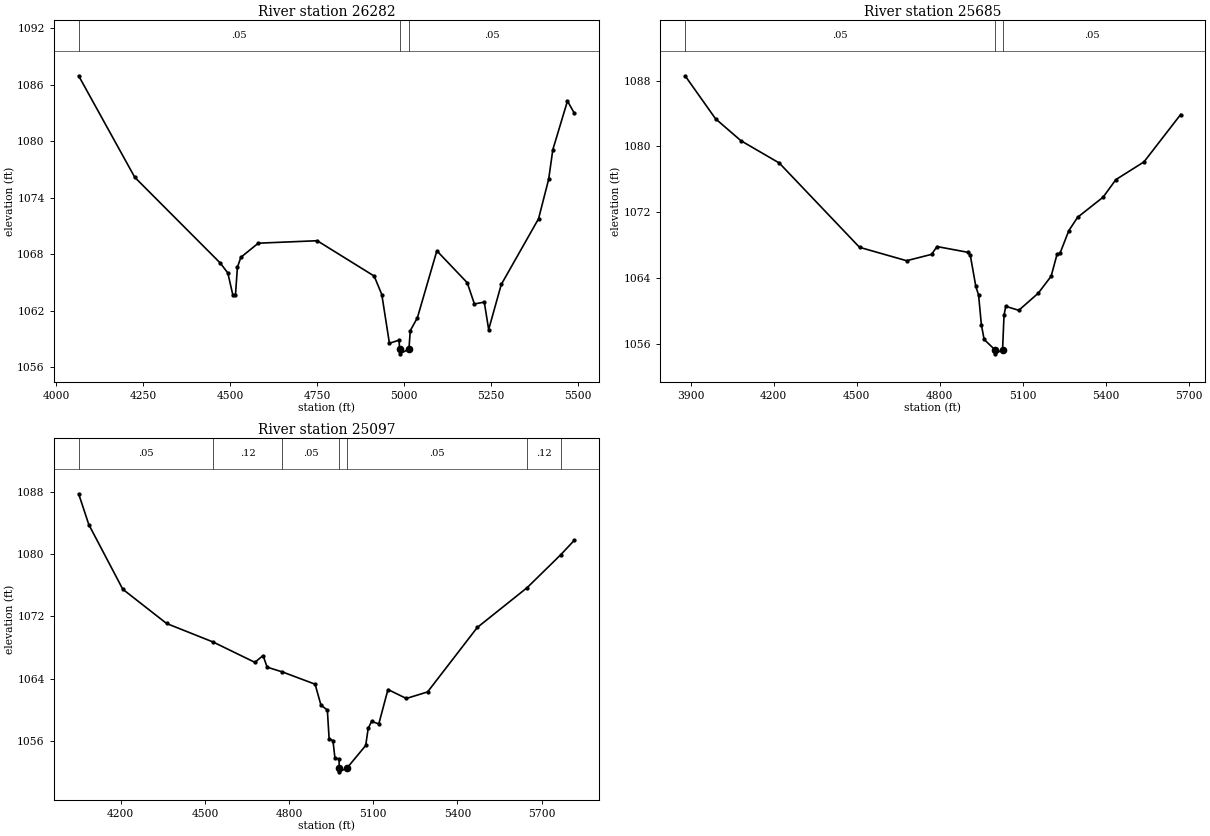
Type RM Length L Ch R = 1,26282,597,597,597
BEGIN DESCRIPTION:
WRIGHTS CREEK 44.0
END DESCRIPTION:
XS GIS Cut Line= 3
      2825555.70     10255503.14      2825110.75     10254680.00
      2825005.69     10254203.14
#Sta/Elev= 30
  4064.3 1086.94  4225.6 1076.17  4471.1 1067.08  4493.0 1066.02  4507.7 1063.64
  4514.9 1063.64  4520.6 1066.62  4530.4 1067.68  4580.6 1069.18  4749.9 1069.44
  4913.6 1065.69  4935.5 1063.73  4957.4 1058.56  4985.1 1058.89  4986.5 1057.94
  4987.0 1057.44  5013.5 1057.94  5017.3 1059.90  5037.8 1061.27  5093.7 1068.37
  5181.1 1064.98  5201.6 1062.73  5230.0 1062.93  5242.6 1060.02  5278.8 1064.80
  5385.9 1071.77  5415.1 1075.98  5426.9 1079.09  5469.0 1084.26  5488.3 1083.00
#Mann=3,-1,0
  4064.3    0.05       0  4986.5    0.05       0  5013.5    0.05       0
Bank Sta=4986.5,5013.5
Exp/Cntr=0.3,0.1

Type RM Length L Ch R = 1,25685,588,588,588
BEGIN DESCRIPTION:
WRIGHTS CREEK 43.0
END DESCRIPTION:
XS GIS Cut Line= 3
      2825605.69     10255503.15      2825577.50     10254383.00
      2825805.67     10253753.15
#Sta/Elev= 30
  3879.5 1088.58  3989.6 1083.35  4081.5 1080.68  4219.6 1077.98  4509.7 1067.73
  4679.8 1066.10  4769.8 1066.87  4789.8 1067.82  4899.9 1067.13  4909.9 1066.77
  4929.9 1062.97  4939.9 1061.92  4949.9 1058.33  4959.9 1056.53  4998.6 1055.28
  4999.1 1054.78  5026.5 1055.28  5031.8 1059.46  5037.9 1060.56  5085.0 1060.07
  5155.1 1062.14  5202.0 1064.21  5223.2 1066.86  5233.9 1066.99  5265.8 1069.75
  5297.7 1071.38  5389.6 1073.82  5436.0 1075.96  5537.4 1078.11  5669.9 1083.87
#Mann=3,-1,0
  3879.5    0.05       0  4998.6    0.03       0  5026.5    0.05       0
Bank Sta=4998.6,5026.5
Exp/Cntr=0.3,0.1

Type RM Length L Ch R = 1,25097,574,574,574
BEGIN DESCRIPTION:
WRIGHTS CREEK 42.0
END DESCRIPTION:
XS GIS Cut Line= 3
      2826855.67     10255153.10      2826095.75     10254583.00
      2825855.68     10253803.11
#Sta/Elev= 30
  4050.0 1087.72  4086.4 1083.76  4207.3 1075.49  4363.5 1071.10  4529.6 1068.72
  4678.1 1066.12  4707.3 1066.99  4721.8 1065.50  4776.3 1064.89  4892.7 1063.32
  4913.5 1060.65  4936.4 1060.00  4942.7 1056.31  4956.3 1056.10  4963.5 1053.84
  4978.1 1053.76  4978.6 1052.59  4979.1 1052.09  5006.7 1052.59  5073.1 1055.47
  5081.8 1057.65  5094.1 1058.56  5119.7 1058.23  5152.4 1062.64  5217.8 1061.49
  5293.6 1062.33  5470.7 1070.59  5648.4 1075.69  5767.9 1079.90  5816.0 1081.74
#Mann=7,-1,0
  4050.0    0.05       0  4529.6    0.12       0  4776.3    0.05       0
  4978.6    0.05       0  5006.7    0.05       0  5648.4    0.12       0
  5767.9    0.05       0
Bank Sta=4978.6,5006.7
Exp/Cntr=0.3,0.1