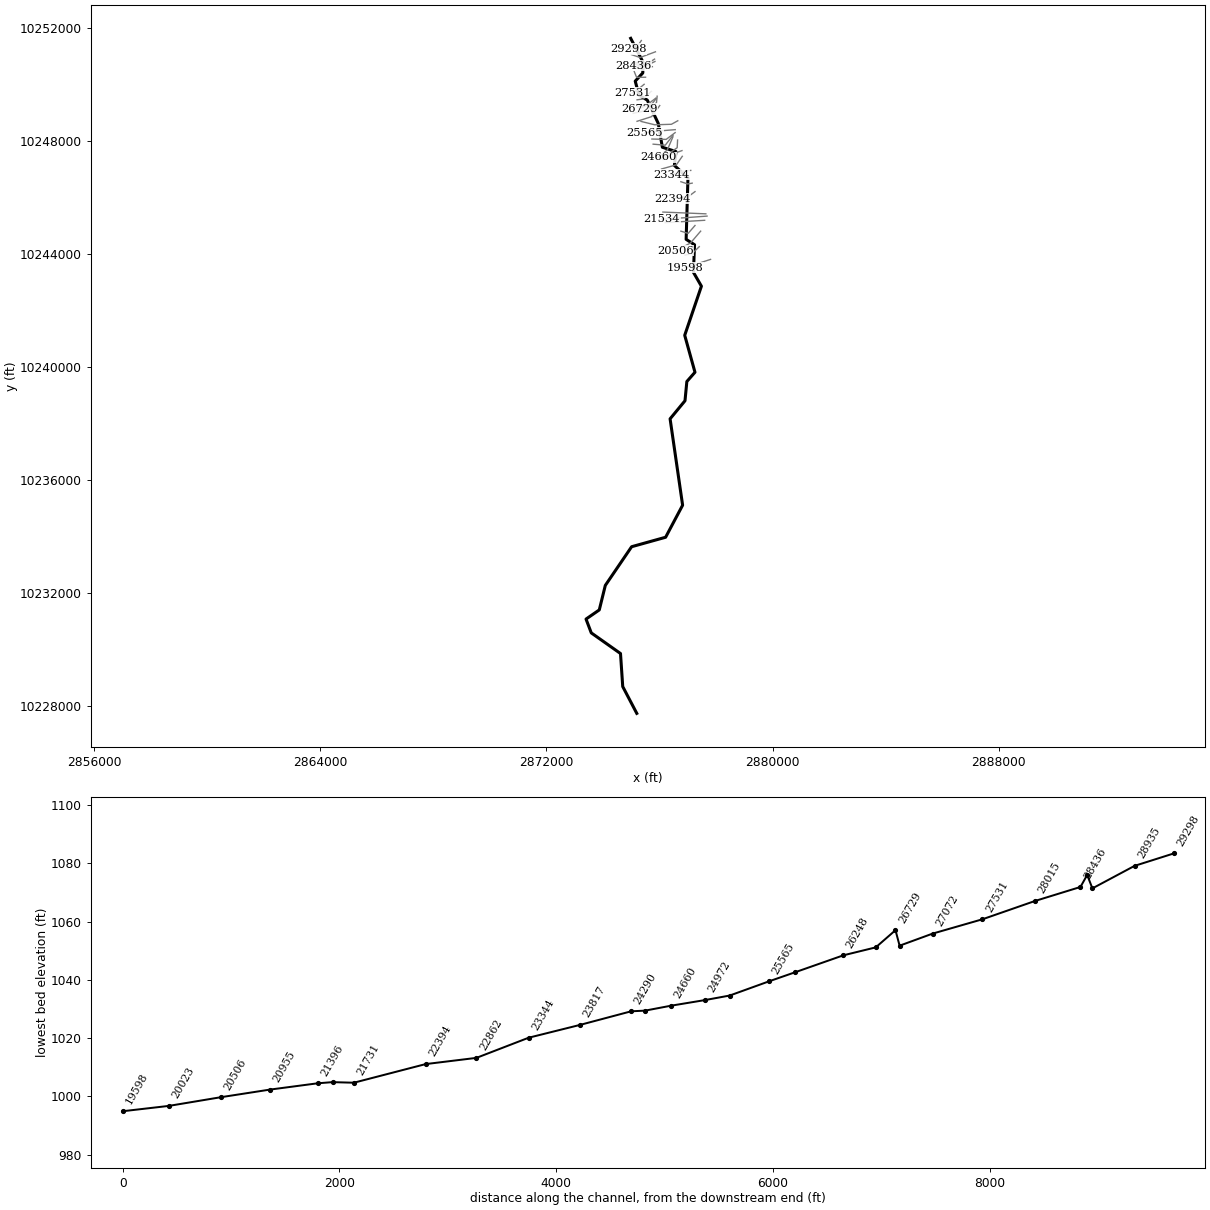
--- SANDY CREEK.prj (project) ---

Proj Title=SANDY CREEK Base Level Engineering
Current Plan=p01
Default Exp/Contr=0.3,0.1
English Units
Geom File=g01
Flow File=f01
Plan File=p01
Y Axis Title=Elevation
X Axis Title(PF)=Main Channel Distance
X Axis Title(XS)=Station
BEGIN DESCRIPTION:
SANDY CREEK
END DESCRIPTION:
DSS Export Rating Curves= 0
DSS Export Rating Curve Sorted= 0
DSS Export Volume Flow Curves= 0
DXF OffsetX= 0
DXF OffsetY= 0
DXF ScaleX= 1
DXF ScaleY= 10

--- SANDY CREEK.p01 (plan) ---

Plan Title=Multiple Run
Short Identifier=Multiple
Geom File=g01
Flow File=f01
Subcritical Flow
K Sum by GR= 0
Std Step Tol= 0.01
Critical Tol= 0.01
Num of Std Step Trials= 20
Max Error Tol= 0.3
Flow Tol Ratio= 0.001
Split Flow NTrial= 30
Split Flow Tol= 0.02
Split Flow Ratio= 0.02
Log Output Level= 0
Friction Slope Method= 1
Unsteady Friction Slope Method= 2
Unsteady Bridges Friction Slope Method= 1
Parabolic Critical Depth
Global Vel Dist=  1 , 1 , 1
Global Log Level= 0
CheckData=True
Encroach Param= -1, 0, 0, 0
BEGIN DESCRIPTION:
Multiple Run
END DESCRIPTION:

--- SANDY CREEK.f01 (steady flow) ---

Flow Title=Multiple
Program Version=4.10
Number of Profiles= 7
Profile Names=10-year,25-year,50-year,1pct_min,100-year,1pct_plu,500-year
River Rch & RM=SANDY CREEK,Reach-1         ,29298
     474     773     935     678    1234    2249    1675
River Rch & RM=SANDY CREEK,Reach-1         ,18739
     567     938    1107     767    1470    2815    1998
River Rch & RM=SANDY CREEK,Reach-1         ,16821
    1039    1774    2409    1705    3285    6331    4448
River Rch & RM=SANDY CREEK,Reach-1         ,15365
    1039    1774    2409    1705    3285    6331    4448
River Rch & RM=SANDY CREEK,Reach-1         ,11029
    1275    2210    3046    2117    4191    8299    5680
River Rch & RM=SANDY CREEK,Reach-1         ,6797
    1684    2980    4088    2751    5677   11715    7690
Boundary for River Rch & Prof#=SANDY CREEK,Reach-1         , 1
Up Type= 0
Dn Type= 3
Dn Slope=0.005
Boundary for River Rch & Prof#=SANDY CREEK,Reach-1         , 2
Up Type= 0
Dn Type= 3
Dn Slope=0.005
Boundary for River Rch & Prof#=SANDY CREEK,Reach-1         , 3
Up Type= 0
Dn Type= 3
Dn Slope=0.005
Boundary for River Rch & Prof#=SANDY CREEK,Reach-1         , 4
Up Type= 0
Dn Type= 3
Dn Slope=0.005
Boundary for River Rch & Prof#=SANDY CREEK,Reach-1         , 5
Up Type= 0
Dn Type= 3
Dn Slope=0.005
Boundary for River Rch & Prof#=SANDY CREEK,Reach-1         , 6
Up Type= 0
Dn Type= 3
Dn Slope=0.005
Boundary for River Rch & Prof#=SANDY CREEK,Reach-1         , 7
Up Type= 0
Dn Type= 3
Dn Slope=0.005
DSS Import GetInterval= 0
DSS Import GetPeak= 0
DSS Import FillOption= 0

--- SANDY CREEK.g01 (geometry) ---

Geom Title=Existing Conditions
Program Version=4.10

River Reach=SANDY CREEK     ,Reach-1
Reach XY= 30
      2874979.75       10251630.        2875413.       10250792.
       2875408.5       10250405.      2875140.25       10250114.
      2875274.25       10249615.      2875565.75       10249444.
       2875955.5       10248617.        2876100.       10247774.
      2876580.75       10247621.        2876526.       10247129.
        2877006.       10246691.      2876941.75       10244513.
       2877238.5       10244322.      2877199.75       10243345.
      2877482.25       10242854.      2876891.25       10241116.
      2877254.25       10239807.      2876966.75       10239479.
      2876901.25       10238798.        2876374.       10238158.
        2876817.       10235099.       2876215.5       10233965.
        2875013.       10233630.      2874081.75       10232260.
      2873868.25       10231392.      2873399.25       10231068.
      2873584.75       10230579.      2874619.25       10229848.
        2874698.       10228678.      2875195.25       10227729.

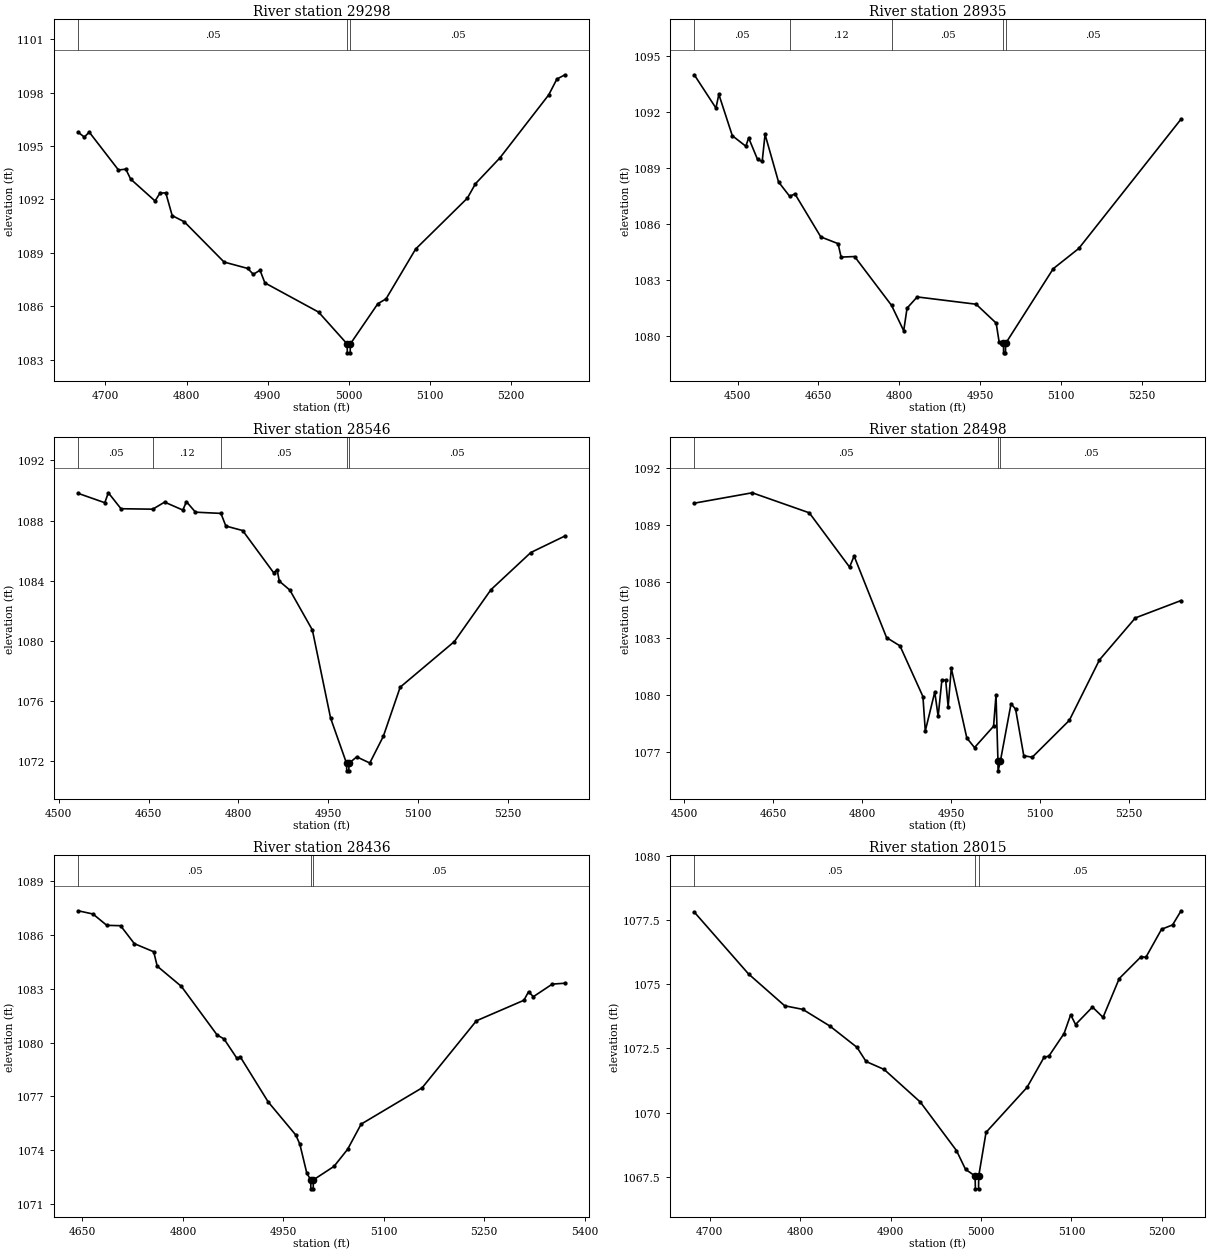
Type RM Length L Ch R = 1 ,29298   ,363,363,363
BEGIN DESCRIPTION:
SANDY CREEK 58.0
END DESCRIPTION:
XS GIS Cut Line= 3
       2875355.7     10251553.14       2875171.5       10251275.
       2874905.7     10251253.11
#Sta/Elev= 30
  4666.4 1095.77    4674  1095.5    4680 1095.78  4716.1 1093.65  4725.1  1093.7
  4731.1 1093.14  4761.2 1091.91  4767.2 1092.35  4774.4 1092.37  4782.3 1091.09
  4797.3 1090.74  4846.3 1088.48  4875.5 1088.12  4882.3 1087.79  4890.6 1088.02
  4896.6 1087.31  4962.8 1085.67    4998 1083.88  4998.3 1083.38  5001.8 1083.38
    5002 1083.88  5035.9 1086.14    5046 1086.41  5082.5 1089.21  5146.3 1092.07
  5156.3 1092.88  5186.4 1094.33  5246.6 1097.87  5256.7 1098.76  5266.7    1099
#Mann= 3 ,-1 , 0
  4666.4     .05       0    4998     .03       0    5002     .05       0
Bank Sta=4998,5002
XS Rating Curve= 0 ,0
Exp/Cntr=0.3,0.1

Type RM Length L Ch R = 1 ,28935   ,389,389,389
BEGIN DESCRIPTION:
SANDY CREEK 57.0
END DESCRIPTION:
XS GIS Cut Line= 3
      2875855.71     10251153.12      2875311.75       10250951.
      2875005.64     10251053.13
#Sta/Elev= 30
  4419.7 1093.97  4459.9 1092.19  4465.3 1092.92  4490.3 1090.71  4515.3 1090.15
  4520.6 1090.59  4537.1 1089.44  4545.7 1089.34    4551 1090.78    4576 1088.24
  4596.7 1087.47  4606.4  1087.6  4654.4  1085.3  4686.4 1084.94  4692.1 1084.22
  4717.1 1084.25  4785.6 1081.64  4808.2 1080.28  4814.4 1081.49  4833.2 1082.09
  4942.5  1081.7  4979.7 1080.69  4985.1  1079.7  4993.2  1079.6  4993.5  1079.1
    4997  1079.1  4997.2  1079.6  5085.6  1083.6  5132.9 1084.68  5322.7  1091.6
#Mann= 5 ,-1 , 0
  4419.7     .05       0  4596.7     .12       0  4785.6     .05       0
  4993.2     .03       0  4997.2     .05       0
Bank Sta=4993.2,4997.2
XS Rating Curve= 0 ,0
Exp/Cntr=0.3,0.1

Type RM Length L Ch R = 1 ,28546   ,48,48,48
BEGIN DESCRIPTION:
Mapping XS eef3483a
END DESCRIPTION:
XS GIS Cut Line= 4
       2875823.9     10250894.66       2875539.8     10250714.22
      2875424.64     10250648.96      2875114.26      10250798.4
#Sta/Elev= 30
  4532.4 1089.81  4576.8 1089.19  4582.8 1089.85  4603.9 1088.79    4657 1088.76
  4676.8 1089.23  4707.3  1088.7  4713.2 1089.26  4728.4 1088.56  4770.9 1088.48
  4779.1 1087.64  4807.2 1087.34  4858.9 1084.54  4864.8 1084.73  4868.4 1083.98
  4886.1 1083.38  4923.7 1080.73  4954.1 1074.88  4980.8 1071.87  4981.1 1071.37
  4984.6 1071.37  4984.8 1071.87  4997.8  1072.3  5019.6 1071.89  5042.2 1073.66
  5070.4 1076.93  5160.9 1079.96  5222.1 1083.41  5288.7 1085.88  5345.8 1086.98
#Mann= 5 ,-1 , 0
  4532.4     .05       0    4657     .12       0  4770.9     .05       0
  4980.8     .05       0  4984.8     .05       0
Bank Sta=4980.8,4984.8
XS Rating Curve= 0 ,0
Exp/Cntr=0.3,0.1

Type RM Length L Ch R = 1 ,28498   ,62,62,62
BEGIN DESCRIPTION:
Mapping XS 328af43f
END DESCRIPTION:
XS GIS Cut Line= 6
      2875839.25      10250810.2      2875493.74     10250645.12
      2875474.54     10250610.57      2875436.16     10250599.06
      2875355.54     10250618.25      2875105.99     10250737.27
#Sta/Elev= 30
  4516.7 1090.15  4614.6  1090.7  4710.9 1089.64  4778.9 1086.77  4786.6 1087.35
  4841.4 1083.04  4864.1  1082.6  4902.8 1079.92  4906.8  1078.1  4922.8 1080.16
  4928.5 1078.87  4934.8 1080.79  4941.2 1080.79  4945.4 1079.38  4950.7 1081.42
  4976.9 1077.73  4989.9 1077.22  5022.1 1078.35  5026.2    1080  5029.5 1076.49
  5029.7 1075.99  5033.5 1076.49  5051.6 1079.54  5059.3 1079.25  5073.1 1076.79
  5087.4 1076.71    5150 1078.66  5200.9 1081.86  5261.5 1084.08  5338.7    1085
#Mann= 3 ,-1 , 0
  4516.7     .05       0  5029.5     .05       0  5033.5     .05       0
Bank Sta=5029.5,5033.5
XS Rating Curve= 0 ,0
Exp/Cntr=0.3,0.1

Type RM Length L Ch R = 1 ,28436   ,421,421,421
BEGIN DESCRIPTION:
Mapping XS 29f7bdee
END DESCRIPTION:
XS GIS Cut Line= 4
      2875747.13     10250625.94      2875405.45     10250541.48
      2875140.58      10250583.7      2875064.98      10250659.3
#Sta/Elev= 30
  4643.6 1087.33  4665.7 1087.15  4686.3 1086.52  4706.9  1086.5  4727.5  1085.5
  4756.4 1085.05  4761.6 1084.25  4797.8 1083.12  4851.1 1080.42  4861.4  1080.2
  4880.7 1079.12  4885.9 1079.19  4927.3  1076.7  4968.7 1074.85  4974.7 1074.34
    4985 1072.74  4990.9 1072.36  4991.1 1071.86  4994.6 1071.86  4994.9 1072.36
  5025.7 1073.11    5046 1074.06  5066.2 1075.46  5157.3 1077.48  5238.4 1081.21
  5309.3 1082.35  5316.3 1082.83  5323.4 1082.55  5351.7 1083.25  5370.7  1083.3
#Mann= 3 ,-1 , 0
  4643.6     .05       0  4990.9     .05       0  4994.9     .05       0
Bank Sta=4990.9,4994.9
XS Rating Curve= 0 ,0
Exp/Cntr=0.3,0.1

Type RM Length L Ch R = 1 ,28015   ,484,484,484
BEGIN DESCRIPTION:
SANDY CREEK 55.0
END DESCRIPTION:
XS GIS Cut Line= 3
      2875505.66     10250253.11       2875188.5       10250248.
      2875105.68     10250453.11
#Sta/Elev= 30
  4682.8 1077.81  4742.8  1075.4  4782.8 1074.16  4802.8 1074.02  4832.8 1073.37
  4862.8 1072.54  4872.8 1071.99  4892.8 1071.68  4932.8 1070.41  4972.8 1068.52
  4982.8 1067.79  4993.4 1067.53  4993.7 1067.03  4997.2 1067.03  4997.4 1067.53
  5005.5 1069.23  5050.8 1070.98  5069.6 1072.15    5075  1072.2  5091.8 1073.08
  5099.1 1073.81  5104.5 1073.43  5123.2 1074.11  5134.9 1073.71  5152.8 1075.22
  5176.9 1076.07  5182.3 1076.05  5199.6 1077.14  5211.8 1077.31  5221.2 1077.86
#Mann= 3 ,-1 , 0
  4682.8     .05       0  4993.4     .03       0  4997.4     .05       0
Bank Sta=4993.4,4997.4
XS Rating Curve= 0 ,0
Exp/Cntr=0.3,0.1

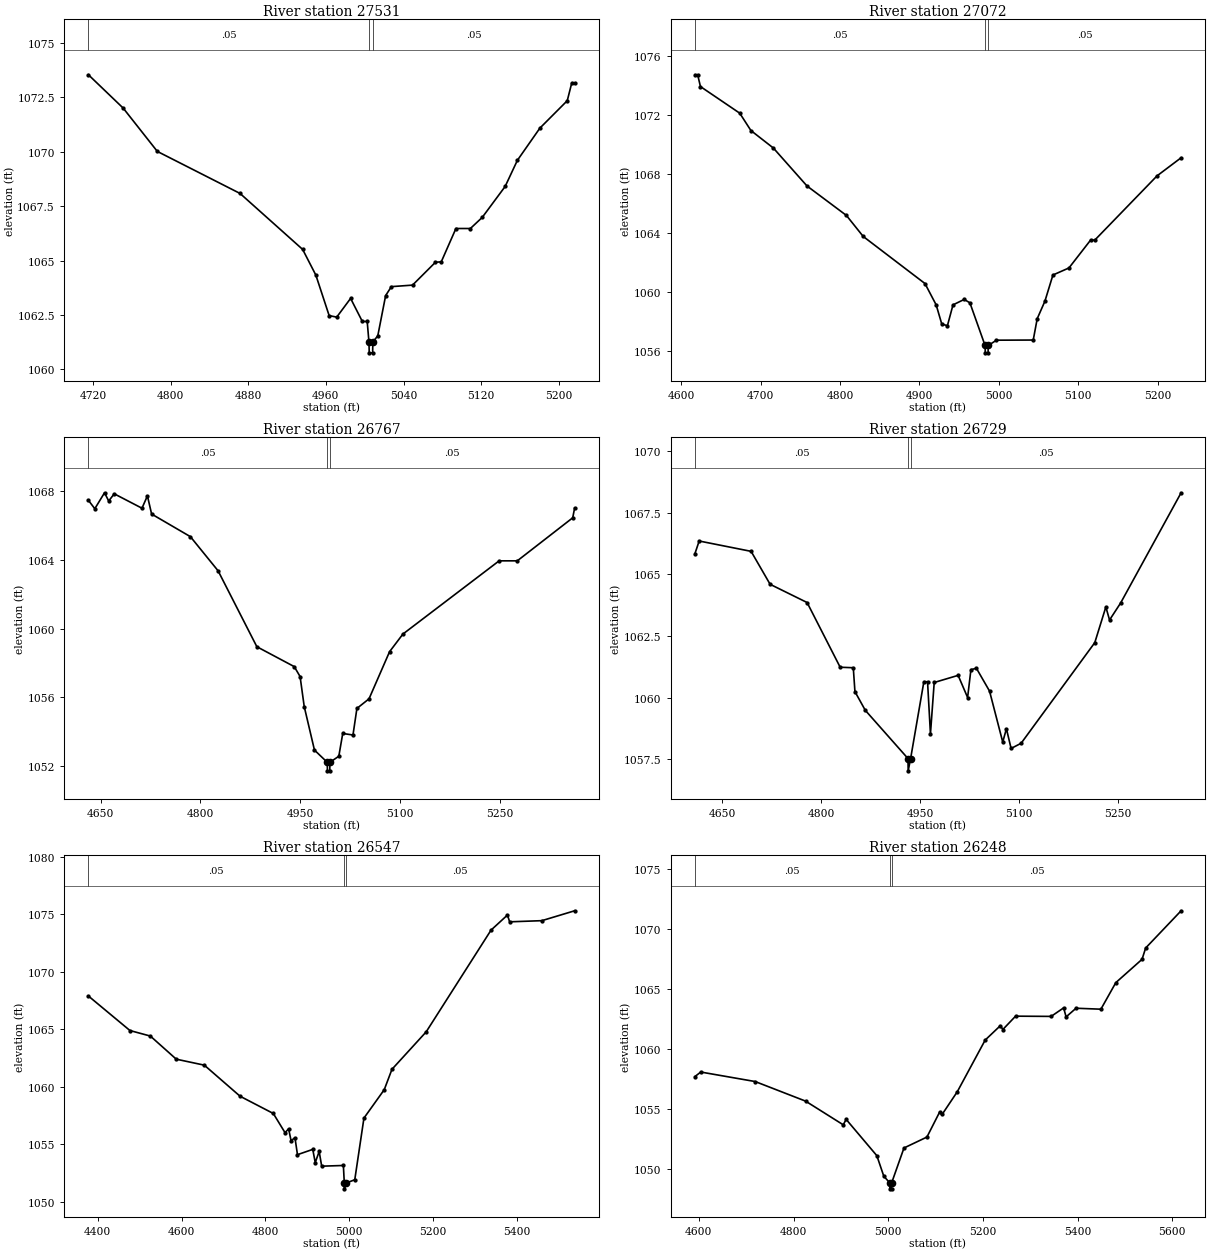
Type RM Length L Ch R = 1 ,27531   ,459,459,459
BEGIN DESCRIPTION:
SANDY CREEK 54.0
END DESCRIPTION:
XS GIS Cut Line= 3
       2875455.7     10250003.12        2875237.       10249821.
      2875055.66      10249703.1
#Sta/Elev= 30
  4715.4 1073.53  4751.2    1072  4786.4 1070.01  4871.6 1068.08  4936.1 1065.51
  4949.7 1064.33  4963.4 1062.47  4971.2  1062.4  4985.5 1063.26  4997.6  1062.2
  5002.6  1062.2  5004.4 1061.26  5004.7 1060.76  5008.2 1060.76  5008.4 1061.26
  5013.5 1061.54  5021.6 1063.39  5027.5  1063.8  5049.3 1063.87  5072.9 1064.92
  5078.9 1064.94    5094 1066.47  5108.9 1066.47  5121.1 1066.98  5144.7  1068.4
  5157.3  1069.6  5180.5 1071.08  5208.7 1072.34  5213.3 1073.15  5216.3 1073.15
#Mann= 3 ,-1 , 0
  4715.4     .05       0  5004.4     .05       0  5008.4     .05       0
Bank Sta=5004.4,5008.4
XS Rating Curve= 0 ,0
Exp/Cntr=0.3,0.1

Type RM Length L Ch R = 1 ,27072   ,305,305,305
BEGIN DESCRIPTION:
SANDY CREEK 53.0
END DESCRIPTION:
XS GIS Cut Line= 3
      2875705.66     10249753.08      2875433.25       10249484.
      2875205.64     10249453.11
#Sta/Elev= 30
  4617.1 1074.75  4620.6 1074.75  4624.1 1073.95  4673.6 1072.14  4687.7 1070.96
    4716 1069.77  4758.4 1067.19    4808 1065.19  4829.2 1063.76    4907 1060.56
  4921.1 1059.11  4928.2  1057.8  4935.3  1057.7  4942.3 1059.11  4956.4 1059.48
  4963.6 1059.25  4982.7 1056.35    4983 1055.85  4986.5 1055.85  4986.7 1056.35
  4997.1 1056.71  5043.4 1056.72  5048.4 1058.17  5058.1 1059.36  5068.2 1061.14
  5088.4 1061.62  5115.9 1063.53  5120.9 1063.51  5199.4 1067.88  5229.7 1069.11
#Mann= 3 ,-1 , 0
  4617.1     .05       0  4982.7     .05       0  4986.7     .05       0
Bank Sta=4982.7,4986.7
XS Rating Curve= 0 ,0
Exp/Cntr=0.3,0.1

Type RM Length L Ch R = 1 ,26767   ,38,38,38
BEGIN DESCRIPTION:
Mapping XS 23d10475
END DESCRIPTION:
XS GIS Cut Line= 4
      2875869.96     10249512.73      2875620.41     10249324.61
       2875539.8     10249274.71      2875225.43     10249198.03
#Sta/Elev= 30
  4631.7 1067.48  4641.3 1066.99  4655.9 1067.92  4662.2 1067.44  4670.5 1067.86
  4712.2 1067.02  4720.4 1067.74  4726.7 1066.68    4785 1065.36  4826.6 1063.37
  4884.9 1058.94  4941.1 1057.78  4949.9  1057.2  4956.1 1055.45  4971.5 1052.91
  4990.7  1052.2    4991  1051.7  4994.5  1051.7  4994.7  1052.2  5008.1 1052.55
    5014 1053.88  5029.4 1053.79  5035.3 1055.34  5053.5  1055.9  5084.4 1058.65
  5104.5 1059.68  5249.1 1063.95  5276.4 1063.95  5359.7 1066.46  5362.6 1067.03
#Mann= 3 ,-1 , 0
  4631.7     .05       0  4990.7     .05       0  4994.7     .05       0
Bank Sta=4990.7,4994.7
XS Rating Curve= 0 ,0
Exp/Cntr=0.3,0.1

Type RM Length L Ch R = 1 ,26729   ,182,182,182
BEGIN DESCRIPTION:
Mapping XS 1503cd76
END DESCRIPTION:
XS GIS Cut Line= 6
      2875881.46     10249497.38      2875735.57     10249309.26
      2875628.09     10249282.39      2875585.87     10249259.35
      2875528.29     10249255.52      2875274.94     10249128.85
#Sta/Elev= 30
  4608.2 1065.84  4614.7 1066.36  4693.5 1065.94  4722.4  1064.6  4778.5 1063.86
  4828.7 1061.23  4848.6 1061.21  4851.1 1060.24  4866.8 1059.48  4931.6 1057.52
  4931.9 1057.02  4935.6 1057.52  4955.7 1060.64  4961.3 1060.64  4965.7 1058.52
  4971.4 1060.61  5007.7  1060.9  5022.1    1060  5027.1 1061.13  5035.4 1061.19
  5055.4 1060.26  5075.4 1058.19    5081 1058.73  5088.1 1057.93  5103.3 1058.14
  5215.1 1062.23  5231.9 1063.68  5237.5 1063.15  5254.3 1063.84  5346.1 1068.32
#Mann= 3 ,-1 , 0
  4608.2     .05       0  4931.6     .05       0  4935.6     .05       0
Bank Sta=4931.6,4935.6
XS Rating Curve= 0 ,0
Exp/Cntr=0.3,0.1

Type RM Length L Ch R = 1 ,26547   ,299,299,299
BEGIN DESCRIPTION:
Mapping XS 6309e039
END DESCRIPTION:
XS GIS Cut Line= 6
        2875916.     10249581.84      2875892.96     10249355.32
      2875789.32     10249240.16      2875593.54     10249117.32
      2875516.77     10249071.26      2875069.15     10248975.61
#Sta/Elev= 30
  4377.7 1067.88  4476.9 1064.88  4525.6  1064.4  4587.5 1062.39  4654.5 1061.87
  4739.8 1059.17  4819.2 1057.67  4847.2    1056  4855.7 1056.34  4861.6 1055.31
  4870.9 1055.56  4876.9 1054.09  4913.4 1054.55  4919.3  1053.4  4928.7 1054.37
  4934.7 1053.09  4986.5 1053.15  4988.7 1051.62  4988.9 1051.12  4992.7 1051.62
  5013.7 1051.91  5035.6 1057.27  5084.1 1059.74  5102.5 1061.51  5184.3 1064.77
  5339.1 1073.61  5378.3 1074.92  5383.5 1074.33  5460.4 1074.43  5538.7 1075.29
#Mann= 3 ,-1 , 0
  4377.7     .05       0  4988.7     .05       0  4992.7     .05       0
Bank Sta=4988.7,4992.7
XS Rating Curve= 0 ,0
Exp/Cntr=0.3,0.1

Type RM Length L Ch R = 1 ,26248   ,444,444,444
BEGIN DESCRIPTION:
SANDY CREEK 51.0
END DESCRIPTION:
XS GIS Cut Line= 3
      2876007.21     10249249.14      2875720.16     10248858.05
      2875204.42     10248692.13
#Sta/Elev= 30
  4591.6 1057.73    4604 1058.11  4718.9 1057.32  4825.4 1055.69  4904.9 1053.72
  4911.1 1054.17  4975.9 1051.15  4990.6 1049.44  5003.2 1048.89  5003.5 1048.39
    5007 1048.39  5007.2 1048.89  5033.2 1051.79  5081.7  1052.7  5108.4 1054.77
  5113.7 1054.58  5145.8 1056.47  5204.7 1060.77  5236.8 1061.97    5242 1061.65
  5268.9 1062.76    5344 1062.74  5370.4 1063.45  5375.6  1062.7  5396.6 1063.42
  5449.1 1063.34  5480.6 1065.55    5536 1067.49  5543.6 1068.43  5618.5 1071.53
#Mann= 3 ,-1 , 0
  4591.6     .05       0  5003.2     .05       0  5007.2     .05       0
Bank Sta=5003.2,5007.2
XS Rating Curve= 0 ,0
Exp/Cntr=0.3,0.1

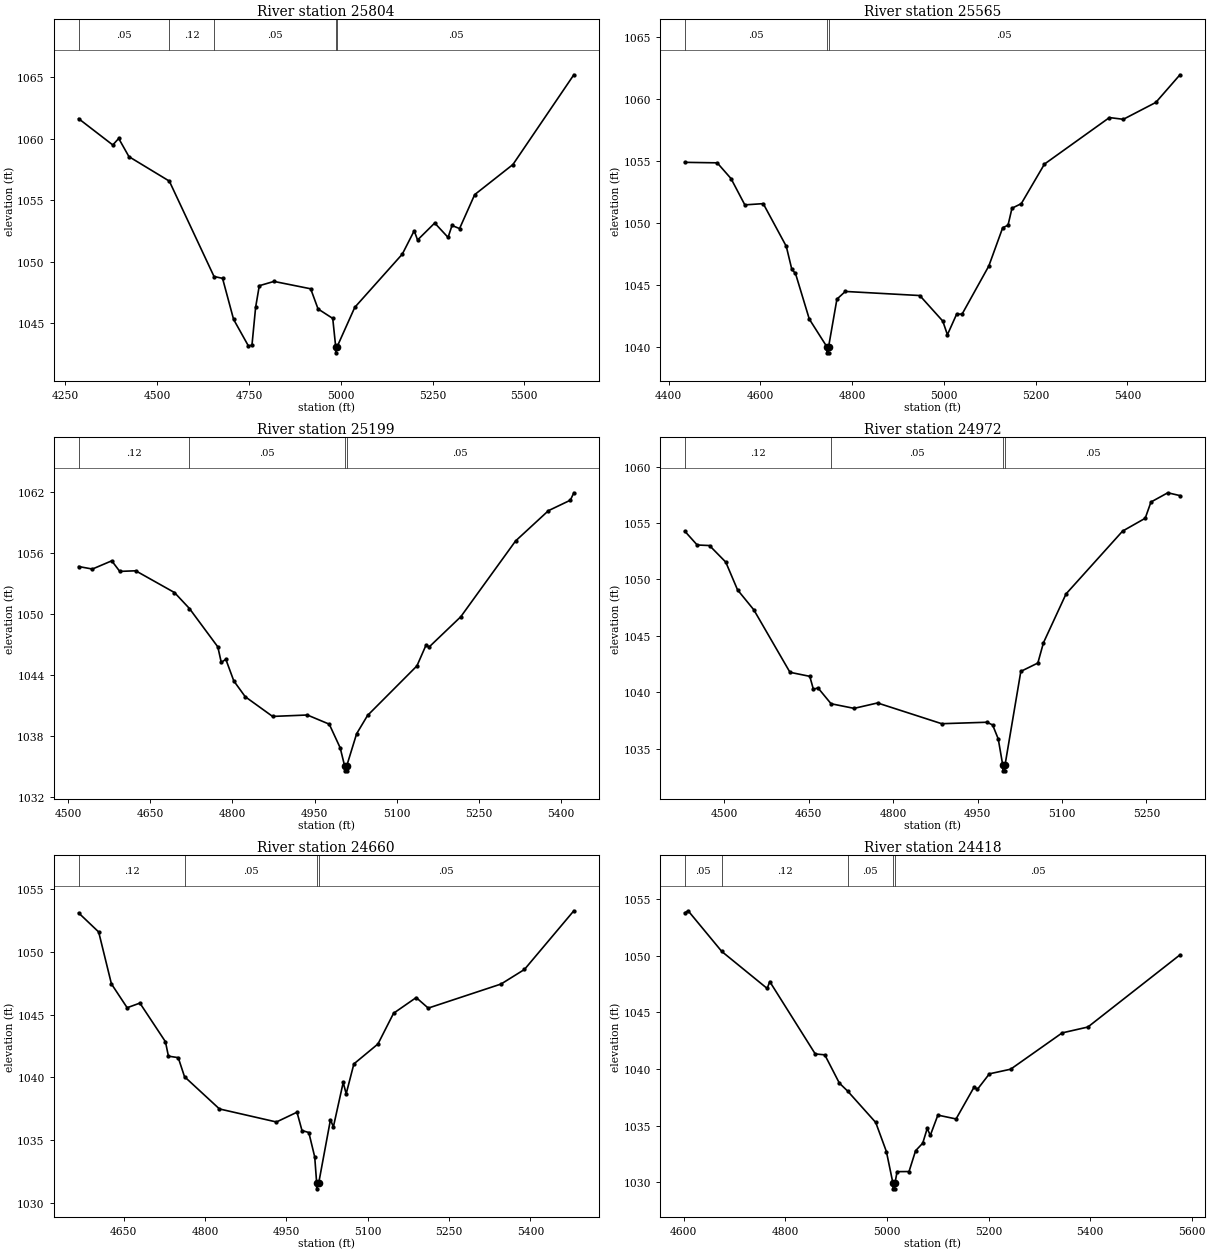
Type RM Length L Ch R = 1 ,25804   ,239,239,239
BEGIN DESCRIPTION:
Mapping XS df8f07fb
END DESCRIPTION:
XS GIS Cut Line= 4
      2876645.63     10248711.27      2876420.58     10248586.78
      2875830.05     10248569.23      2875343.33     10248688.52
#Sta/Elev= 30
  4285.8 1061.64  4378.9  1059.5    4395 1060.03  4422.9 1058.55  4532.9 1056.56
  4654.7  1048.8  4677.9 1048.65    4708 1045.31    4748 1043.17    4758  1043.2
    4768 1046.29    4778 1048.05    4818  1048.4    4918  1047.8  4938.1 1046.16
  4978.1 1045.39  4986.1 1043.09  4986.3 1042.59  4990.1 1043.09  5038.1 1046.29
  5167.6 1050.62    5200 1052.52  5209.2 1051.77  5255.9 1053.15  5292.3 1051.98
    5303 1052.95  5323.6  1052.7  5364.8 1055.46    5469 1057.91  5634.9 1065.21
#Mann= 5 ,-1 , 0
  4285.8     .05       0  4532.9     .12       0  4654.7     .05       0
  4986.1     .05       0  4990.1     .05       0
Bank Sta=4986.1,4990.1
XS Rating Curve= 0 ,0
Exp/Cntr=0.3,0.1

Type RM Length L Ch R = 1 ,25565   ,366,366,366
BEGIN DESCRIPTION:
Mapping XS b7c409dd
END DESCRIPTION:
XS GIS Cut Line= 4
      2876556.26     10248396.85      2876087.01     10248358.55
       2875887.5     10248342.59      2875483.69     10248281.93
#Sta/Elev= 30
  4435.2 1054.86    4506 1054.82  4536.1 1053.55  4566.2 1051.43  4606.3 1051.53
  4656.5 1048.09  4668.6 1046.23  4676.6  1045.9  4706.7 1042.22  4744.8    1040
  4745.1  1039.5  4748.6  1039.5  4748.8    1040  4766.9 1043.83  4785.2 1044.45
  4947.5 1044.12  4997.6 1042.06  5007.7 1040.96  5027.7 1042.61  5039.8 1042.63
  5097.9  1046.5  5128.2 1049.59  5139.8 1049.79  5148.4 1051.16  5168.7 1051.53
  5219.2 1054.72  5360.8 1058.47  5391.1 1058.33  5461.9 1059.69  5514.5 1061.92
#Mann= 3 ,-1 , 0
  4435.2     .05       0  4744.8     .03       0  4748.8     .05       0
Bank Sta=4744.8,4748.8
XS Rating Curve= 0 ,0
Exp/Cntr=0.3,0.1

Type RM Length L Ch R = 1 ,25199   ,227,227,227
BEGIN DESCRIPTION:
SANDY CREEK 50.0
END DESCRIPTION:
XS GIS Cut Line= 3
      2876553.05     10248291.51      2876235.44     10248052.11
      2875729.33     10248064.84
#Sta/Elev= 30
  4519.1 1054.67  4544.2 1054.42  4579.6 1055.23  4594.2 1054.19  4623.3 1054.25
  4694.1 1052.11  4721.4 1050.54  4773.2 1046.77  4779.5 1045.24  4787.8 1045.55
  4802.4 1043.42  4823.2 1041.87  4873.2 1039.93  4936.6 1040.07  4976.6 1039.17
  4996.6 1036.84  5004.6 1035.08  5004.9 1034.58  5008.4 1034.58  5008.6 1035.08
  5026.6 1038.23  5046.6 1040.03  5136.7  1044.9  5153.6 1046.98  5158.6 1046.74
  5216.7 1049.73  5316.7 1057.18  5376.7 1060.16  5416.7 1061.19  5423.1 1061.92
#Mann= 4 ,-1 , 0
  4519.1     .12       0  4721.4     .05       0  5004.6     .05       0
  5008.6     .05       0
Bank Sta=5004.6,5008.6
XS Rating Curve= 0 ,0
Exp/Cntr=0.3,0.1

Type RM Length L Ch R = 1 ,24972   ,312,312,312
BEGIN DESCRIPTION:
SANDY CREEK 49.0
END DESCRIPTION:
XS GIS Cut Line= 3
      2876479.62     10248200.52      2876201.93     10247846.22
      2875774.16     10247882.93
#Sta/Elev= 30
    4430 1054.29  4452.1 1053.06    4474 1053.01  4502.9 1051.54  4523.8 1049.08
  4552.7 1047.31  4616.9 1041.77  4652.1 1041.41  4658.5 1040.26  4666.6 1040.39
  4689.9 1038.98  4730.8 1038.57  4772.4 1039.05  4886.4 1037.21  4966.7 1037.34
  4976.8  1037.1  4986.8 1035.86  4994.8 1033.53  4995.1 1033.03  4998.6 1033.03
  4998.8 1033.53  5026.9 1041.85  5057.1 1042.59  5067.1 1044.39  5107.2 1048.72
  5207.6 1054.29  5247.8 1055.43    5258 1056.87  5287.9 1057.69  5309.5 1057.44
#Mann= 4 ,-1 , 0
    4430     .12       0  4689.9     .05       0  4994.8     .05       0
  4998.8     .05       0
Bank Sta=4994.8,4998.8
XS Rating Curve= 0 ,0
Exp/Cntr=0.3,0.1

Type RM Length L Ch R = 1 ,24660   ,242,242,242
BEGIN DESCRIPTION:
SANDY CREEK 48.0
END DESCRIPTION:
XS GIS Cut Line= 3
      2876474.85     10248143.09      2876273.75     10247675.44
      2875960.04     10247420.65
#Sta/Elev= 30
  4566.9 1053.11  4603.9 1051.59  4627.4 1047.45  4656.4 1045.55  4679.9 1045.92
    4727 1042.84  4732.5 1041.69  4750.6 1041.57  4762.2 1040.05  4826.6 1037.48
  4931.7 1036.44  4969.6 1037.22  4978.8 1035.76  4991.4  1035.6  5002.3 1033.65
  5005.8 1031.61    5006 1031.11  5009.8 1031.61  5031.3 1036.62  5036.7 1036.05
  5054.8 1039.59  5060.3 1038.69  5074.5 1041.07  5118.9 1042.66  5147.7 1045.11
  5189.4 1046.36  5211.6 1045.52  5345.9 1047.44    5389  1048.6  5480.1 1053.28
#Mann= 4 ,-1 , 0
  4566.9     .12       0  4762.2     .05       0  5005.8     .05       0
  5009.8     .05       0
Bank Sta=5005.8,5009.8
XS Rating Curve= 0 ,0
Exp/Cntr=0.3,0.1

Type RM Length L Ch R = 1 ,24418   ,128,128,128
BEGIN DESCRIPTION:
SANDY CREEK 47.0
END DESCRIPTION:
XS GIS Cut Line= 3
      2876639.24     10248029.76      2876624.88     10247756.84
      2876047.32     10247357.97
#Sta/Elev= 30
  4601.8 1053.81  4608.5 1053.99  4674.8 1050.39  4764.2 1047.12  4769.2 1047.73
  4858.8 1041.33  4877.6 1041.25  4906.3 1038.75  4922.5 1038.05  4977.9 1035.27
  4998.9  1032.7  5011.8  1029.9    5012  1029.4  5015.5  1029.4  5015.8  1029.9
    5020 1030.92  5043.5 1030.93  5056.4 1032.77  5070.5 1033.44  5079.3 1034.74
  5085.4 1034.13  5100.3 1035.92  5136.1 1035.58  5171.9 1038.42    5178 1038.19
  5201.7 1039.57  5243.6 1039.98    5345 1043.19  5395.7 1043.71    5577 1050.09
#Mann= 5 ,-1 , 0
  4601.8     .05       0  4674.8     .12       0  4922.5     .05       0
  5011.8     .05       0  5015.8     .05       0
Bank Sta=5011.8,5015.8
XS Rating Curve= 0 ,0
Exp/Cntr=0.3,0.1

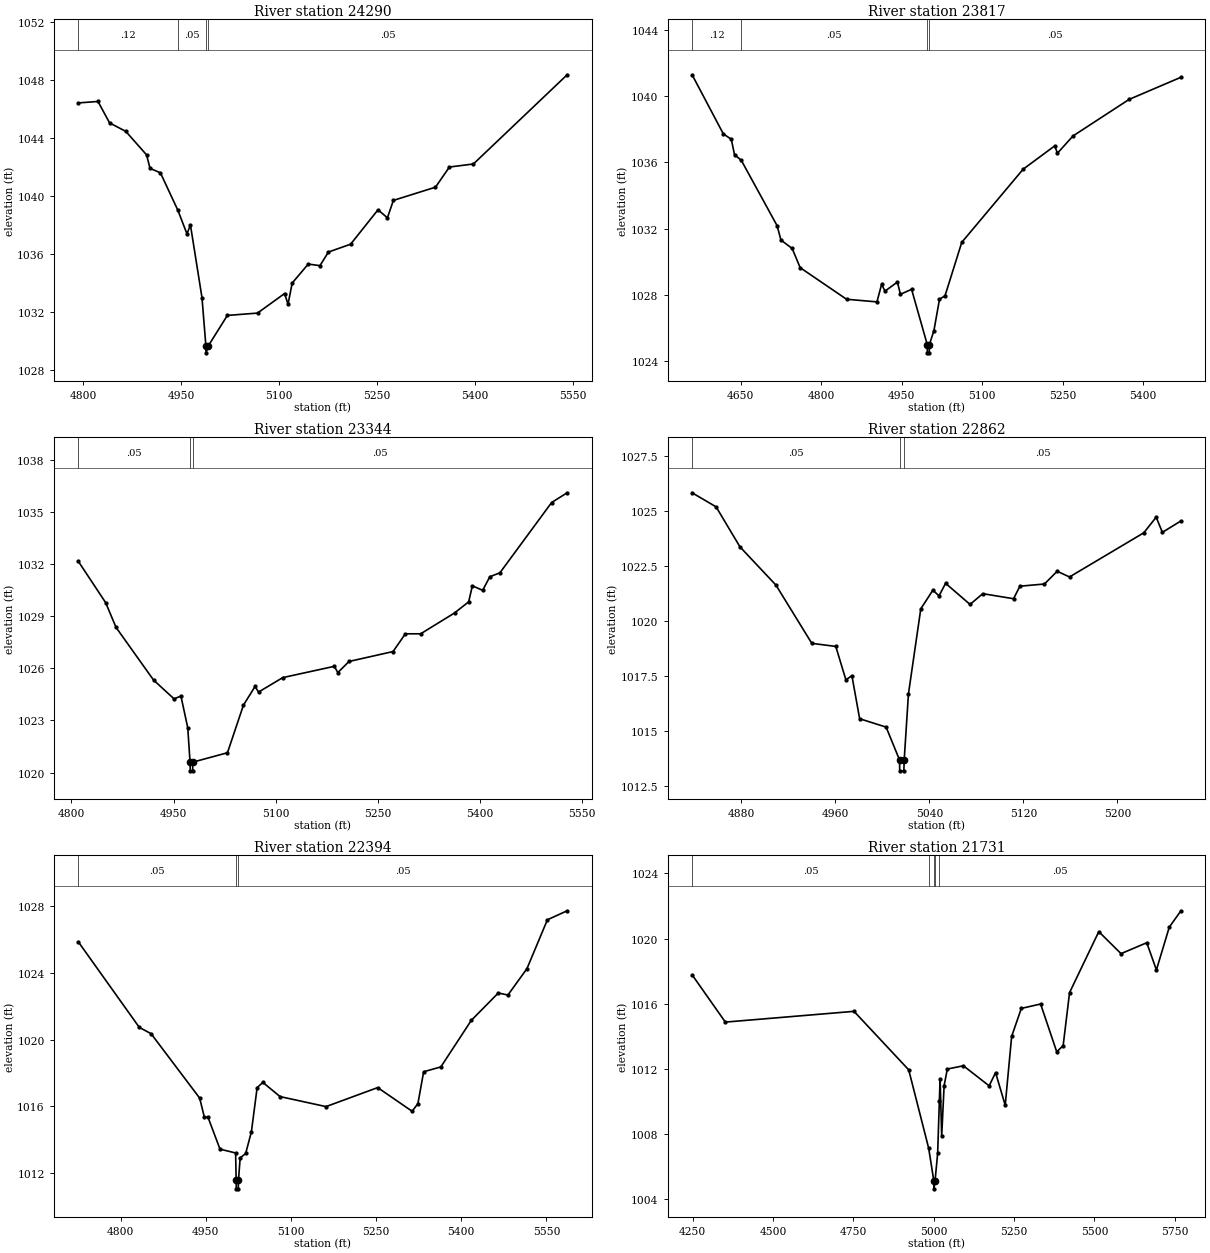
Type RM Length L Ch R = 1 ,24290   ,473,473,473
BEGIN DESCRIPTION:
Mapping XS 9740f8dd
END DESCRIPTION:
XS GIS Cut Line= 3
      2876794.09      10247654.7      2876401.43     10247515.83
      2876118.98     10247342.87
#Sta/Elev= 30
  4792.8  1046.4  4822.9  1046.5  4840.7 1045.02  4865.4 1044.44  4897.2 1042.82
  4902.5 1041.89  4918.4 1041.58  4945.1    1039    4959 1037.37  4964.3 1037.99
    4982 1032.97  4987.9 1029.67  4988.2 1029.17  4991.9 1029.67  5020.8 1031.75
  5066.9 1031.91  5108.3 1033.26  5113.6 1032.52  5119.9 1033.98  5144.5 1035.29
  5162.4 1035.18  5175.4 1036.12  5209.3 1036.66  5251.2 1039.03  5265.6 1038.48
  5274.7 1039.68  5339.1 1040.59  5360.4 1041.98  5397.1 1042.19  5540.5 1048.34
#Mann= 4 ,-1 , 0
  4792.8     .12       0  4945.1     .05       0  4987.9     .05       0
  4991.9     .05       0
Bank Sta=4987.9,4991.9
XS Rating Curve= 0 ,0
Exp/Cntr=0.3,0.1

Type RM Length L Ch R = 1 ,23817   ,473,473,473
BEGIN DESCRIPTION:
SANDY CREEK 46.0
END DESCRIPTION:
XS GIS Cut Line= 3
       2876805.7     10247453.13      2876596.84      10247152.4
      2876072.56     10247004.84
#Sta/Elev= 30
  4559.4  1041.3  4617.5 1037.73  4632.4  1037.4  4638.4 1036.47    4651 1036.13
  4717.7 1032.18  4724.9 1031.31  4745.8  1030.8  4760.7 1029.64  4847.1 1027.73
  4903.8 1027.57  4912.5 1028.64  4918.7 1028.22  4941.9 1028.77  4947.5 1028.03
  4968.3 1028.33  4997.5 1024.99  4997.7 1024.49  5001.2 1024.49  5001.5 1024.99
  5009.9 1025.83  5020.3 1027.73  5030.6 1027.94  5061.8 1031.17  5176.1 1035.59
  5234.9    1037  5240.1 1036.56    5269  1037.6  5373.5 1039.81  5470.2 1041.15
#Mann= 4 ,-1 , 0
  4559.4     .12       0    4651     .05       0  4997.5     .05       0
  5001.5     .05       0
Bank Sta=4997.5,5001.5
XS Rating Curve= 0 ,0
Exp/Cntr=0.3,0.1

Type RM Length L Ch R = 1 ,23344   ,482,482,482
BEGIN DESCRIPTION:
SANDY CREEK 45.0
END DESCRIPTION:
XS GIS Cut Line= 3
      2877105.73     10246953.12       2876916.5       10246936.
       2876405.7     10246803.12
#Sta/Elev= 30
    4810 1032.15  4850.2 1029.77  4865.4 1028.35  4920.5 1025.32  4950.6 1024.24
  4960.7  1024.4  4970.7 1022.58  4974.1  1020.6  4974.4  1020.1  4977.9  1020.1
  4978.1  1020.6    5029 1021.14  5052.5 1023.88  5069.5 1024.95  5074.7 1024.63
  5110.1 1025.46  5185.9 1026.11  5191.1 1025.75  5207.5 1026.39  5272.2 1026.96
  5290.2 1027.98  5312.7 1027.98  5362.5 1029.18  5383.2 1029.82  5388.6 1030.74
  5403.8 1030.48  5414.2 1031.26  5429.1 1031.49    5505 1035.53  5527.8 1036.09
#Mann= 3 ,-1 , 0
    4810     .05       0  4974.1     .05       0  4978.1     .05       0
Bank Sta=4974.1,4978.1
XS Rating Curve= 0 ,0
Exp/Cntr=0.3,0.1

Type RM Length L Ch R = 1 ,22862   ,468,468,468
BEGIN DESCRIPTION:
SANDY CREEK 44.0
END DESCRIPTION:
XS GIS Cut Line= 3
      2877155.72     10246503.12      2876996.75       10246473.
      2876755.71      10246553.1
#Sta/Elev= 30
  4838.2 1025.83  4858.6 1025.19  4878.9 1023.37  4909.5 1021.63    4940 1018.98
  4960.4 1018.84    4969 1017.32  4974.1 1017.51  4980.7 1015.55  5003.2 1015.17
  5014.6 1013.68  5014.8 1013.18  5018.3 1013.18  5018.6 1013.68  5022.2 1016.68
  5032.7 1020.55    5043  1021.4  5048.2 1021.14  5053.8 1021.71  5074.6 1020.75
  5085.4 1021.24  5111.6 1021.01    5117 1021.58  5137.9 1021.68  5148.7 1022.26
  5159.2    1022  5222.4 1024.01  5232.9 1024.72  5238.2 1024.03    5254 1024.55
#Mann= 3 ,-1 , 0
  4838.2     .05       0  5014.6     .05       0  5018.6     .05       0
Bank Sta=5014.6,5018.6
XS Rating Curve= 0 ,0
Exp/Cntr=0.3,0.1

Type RM Length L Ch R = 1 ,22394   ,663,663,663
BEGIN DESCRIPTION:
SANDY CREEK 43.0
END DESCRIPTION:
XS GIS Cut Line= 3
      2877255.67      10246203.1      2877035.75       10246039.
      2876455.67     10245953.11
#Sta/Elev= 30
  4725.6 1025.86    4833 1020.73  4853.8 1020.35  4939.3 1016.49  4947.6 1015.34
  4953.9 1015.35  4975.1 1013.43  5002.6  1013.2  5003.6 1011.55  5003.8 1011.05
  5007.3 1011.05  5007.6 1011.55  5010.6  1012.9  5020.3 1013.17  5030.4 1014.47
  5040.5 1017.12  5050.6 1017.43  5080.9 1016.58  5161.8 1015.98  5252.8 1017.12
  5313.4  1015.7  5323.6 1016.16  5333.7 1018.07    5364 1018.36  5417.6 1021.15
  5465.1 1022.79  5482.1 1022.67  5515.6 1024.25  5551.6 1027.18  5586.4 1027.72
#Mann= 3 ,-1 , 0
  4725.6     .05       0  5003.6     .05       0  5007.6     .05       0
Bank Sta=5003.6,5007.6
XS Rating Curve= 0 ,0
Exp/Cntr=0.3,0.1

Type RM Length L Ch R = 1 ,21731   ,197,197,197
BEGIN DESCRIPTION:
Mapping XS 531fbbfe
END DESCRIPTION:
XS GIS Cut Line= 2
      2877638.99     10245416.33      2876119.37     10245478.78
#Sta/Elev= 30
  4248.2 1017.78  4351.6 1014.88  4751.9 1015.54  4922.1 1011.95  4984.2 1007.14
  5000.1 1005.15  5000.4 1004.65  5004.1 1005.15  5012.1 1006.83  5017.4 1010.02
  5019.7 1011.41  5024.7 1007.89  5032.2 1010.98  5042.2    1012  5092.2  1012.2
  5172.3 1010.97  5192.3 1011.78  5222.3 1009.78  5242.3    1014  5272.4 1015.72
  5332.4 1015.99  5382.5 1013.06  5402.5 1013.43  5422.5 1016.69  5513.4 1020.43
  5582.6 1019.08  5662.7 1019.75  5692.7 1018.08  5732.8 1020.71  5769.1 1021.71
#Mann= 5 ,-1 , 0
  4248.2     .05       0  4984.2     .12       0  5000.1     .07       0
  5004.1     .12       0  5017.4     .05       0
Bank Sta=5000.1,5004.1
XS Rating Curve= 0 ,0
Exp/Cntr=0.3,0.1

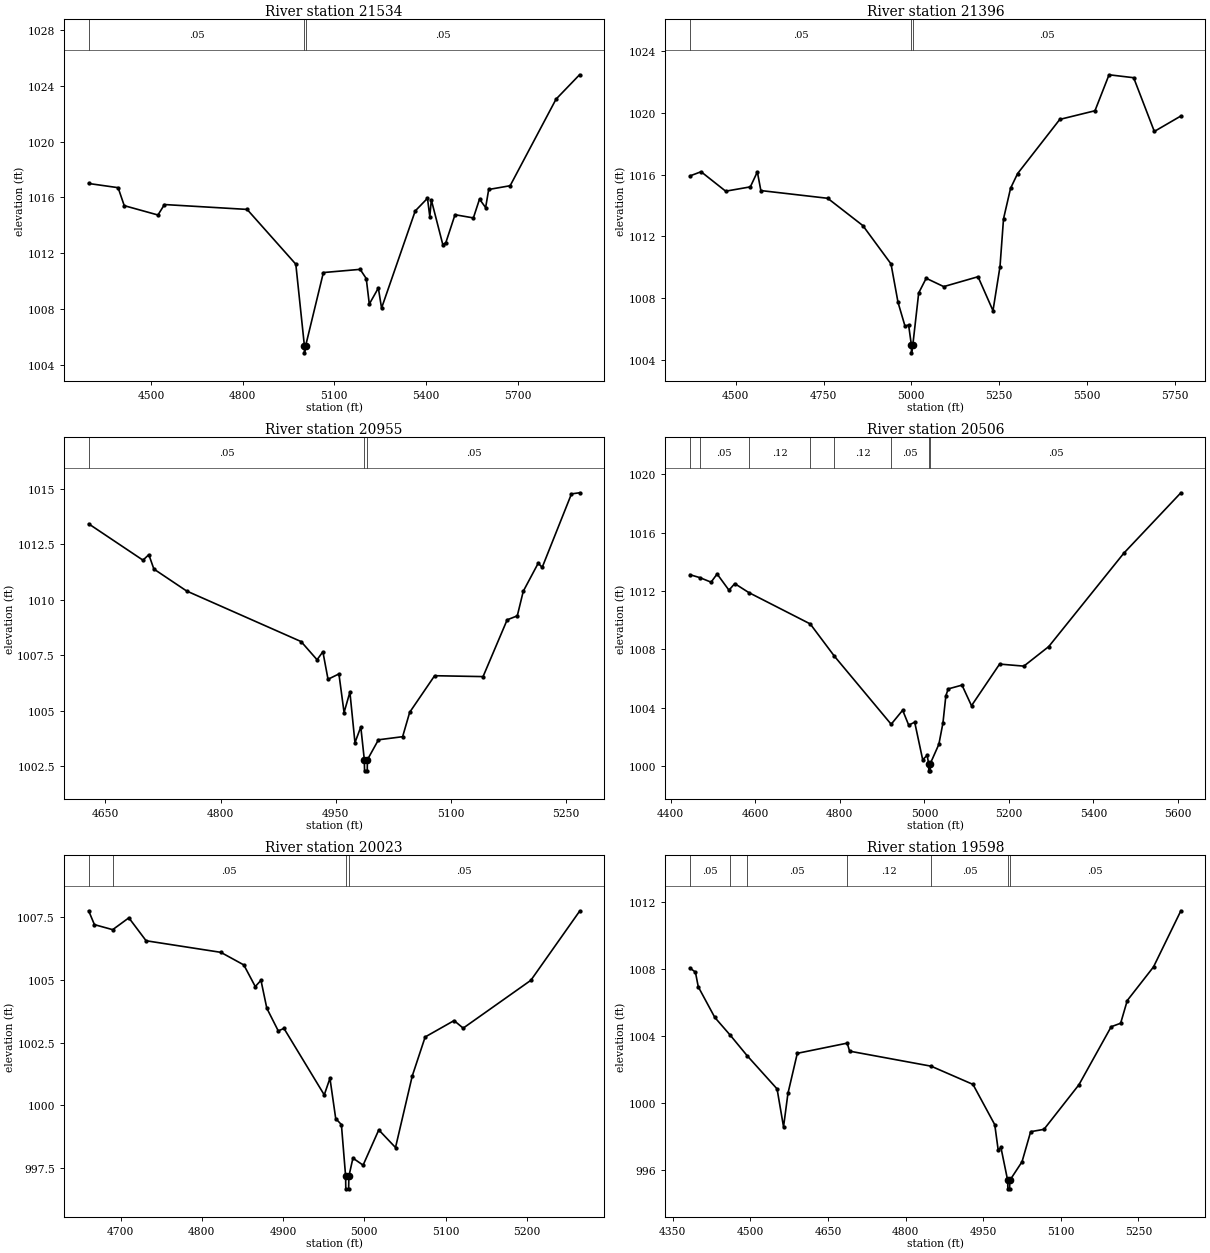
Type RM Length L Ch R = 1 ,21534   ,138,138,138
BEGIN DESCRIPTION:
Mapping XS fe558d50
END DESCRIPTION:
XS GIS Cut Line= 3
      2877681.82     10245336.22      2876906.37     10245278.63
      2876078.95     10245228.83
#Sta/Elev= 30
    4296    1017  4392.4  1016.7  4412.5 1015.41  4522.8 1014.74  4544.1 1015.49
  4814.6 1015.14    4974 1011.21  5002.1 1005.35  5002.3 1004.85  5006.1 1005.35
  5064.2 1010.61  5184.5 1010.84  5204.5 1010.18  5214.5 1008.35  5244.1  1009.5
  5254.6 1008.06  5364.8 1015.03  5404.9 1015.94  5412.5 1014.62  5417.5 1015.82
    5455 1012.62    5465 1012.76    5495 1014.76  5555.1 1014.53  5575.2 1015.88
  5595.2 1015.27  5605.2 1016.57  5675.4 1016.84  5825.6 1023.05  5902.5  1024.8
#Mann= 3 ,-1 , 0
    4296     .05       0  5002.1     .03       0  5006.1     .05       0
Bank Sta=5002.1,5006.1
XS Rating Curve= 0 ,0
Exp/Cntr=0.3,0.1

Type RM Length L Ch R = 1 ,21396   ,441,441,441
BEGIN DESCRIPTION:
Mapping XS 8c5d00aa
END DESCRIPTION:
XS GIS Cut Line= 2
      2877597.24     10245187.16      2876201.43     10245103.83
#Sta/Elev= 30
  4369.5 1015.91  4401.1 1016.18  4471.2 1014.92  4541.4  1015.2  4561.4 1016.17
  4571.4 1014.96  4761.8 1014.46    4862 1012.69  4942.1 1010.21  4962.1 1007.72
  4982.1 1006.17  4992.2 1006.26  5000.2 1004.95  5000.4 1004.45  5004.2 1004.95
    5021 1008.33  5042.3 1009.28  5092.3 1008.74    5190 1009.38  5232.6 1007.18
  5252.6 1010.04  5262.6 1013.13  5282.7 1015.11  5302.7 1016.06  5422.9 1019.57
  5523.1 1020.13  5563.2 1022.46  5633.3 1022.27  5692.2 1018.79  5767.8 1019.79
#Mann= 3 ,-1 , 0
  4369.5     .05       0  5000.2     .05       0  5004.2     .05       0
Bank Sta=5000.2,5004.2
XS Rating Curve= 0 ,0
Exp/Cntr=0.3,0.1

Type RM Length L Ch R = 1 ,20955   ,449,449,449
BEGIN DESCRIPTION:
SANDY CREEK 40.0
END DESCRIPTION:
XS GIS Cut Line= 3
      2877255.71     10245003.14      2877011.25       10244723.
      2876755.71      10244803.1
#Sta/Elev= 30
  4628.2 1013.42    4699 1011.78  4706.6 1012.03  4713.2 1011.38  4755.9 1010.39
    4905 1008.11  4925.8 1007.29  4933.4 1007.65  4940.1 1006.41  4954.3 1006.65
    4961 1004.91  4968.6 1005.83  4975.2 1003.55  4982.8 1004.26  4987.4 1002.78
  4987.7 1002.28  4991.2 1002.28  4991.4 1002.78  5005.8 1003.68  5037.3 1003.82
  5046.5 1004.92    5079 1006.57  5142.1 1006.53  5173.5 1009.09  5186.7 1009.27
  5194.5 1010.38  5213.9 1011.64  5219.2 1011.46  5257.3 1014.77  5267.8 1014.82
#Mann= 3 ,-1 , 0
  4628.2     .05       0  4987.4     .05       0  4991.4     .05       0
Bank Sta=4987.4,4991.4
XS Rating Curve= 0 ,0
Exp/Cntr=0.3,0.1

Type RM Length L Ch R = 1 ,20506   ,483,483,483
BEGIN DESCRIPTION:
SANDY CREEK 39.0
END DESCRIPTION:
XS GIS Cut Line= 3
      2877455.67     10244803.09      2877094.75       10244382.
      2876555.72     10244103.13
#Sta/Elev= 30
  4445.4 1013.12  4468.7 1012.92  4495.3 1012.61  4509.6 1013.17  4537.6 1012.06
  4551.3 1012.51  4584.4  1011.9  4729.9 1009.75  4787.1 1007.54  4921.4 1002.88
  4948.6 1003.84  4962.9 1002.82  4977.1 1003.02    4996 1000.45  5006.5 1000.75
  5010.1 1000.19  5010.4  999.69  5013.9  999.69  5014.1 1000.19  5034.3 1001.51
    5044 1002.98  5050.8 1004.83  5056.4  1005.3    5089 1005.56  5111.5 1004.15
    5178    1007  5235.4 1006.86  5294.3  1008.2  5471.8 1014.59  5606.9 1018.73
#Mann= 8 ,-1 , 0
  4445.4     .12       0  4468.7     .05       0  4584.4     .12       0
  4729.9     .05       0  4787.1     .12       0  4921.4     .05       0
  5010.1     .03       0  5014.1     .05       0
Bank Sta=5010.1,5014.1
XS Rating Curve= 0 ,0
Exp/Cntr=0.3,0.1

Type RM Length L Ch R = 1 ,20023   ,425,425,425
BEGIN DESCRIPTION:
SANDY CREEK 38.0
END DESCRIPTION:
XS GIS Cut Line= 3
      2877405.69     10244253.12        2877163.       10244016.
      2876905.67     10243953.11
#Sta/Elev= 30
  4660.7 1007.73  4667.8 1007.18  4690.3 1006.98  4710.2 1007.45  4731.4 1006.54
  4823.4 1006.08  4851.7 1005.58  4865.8 1004.72  4872.8 1004.97    4880 1003.86
  4894.1 1002.96  4901.1 1003.06  4950.7 1000.42  4957.7 1001.08  4964.8  999.48
  4971.8  999.24    4977  997.19  4977.2  996.69  4980.7  996.69    4981  997.19
    4986  997.91  4998.5  997.63  5017.8  999.03  5038.4  998.33    5059 1001.17
  5074.9 1002.72  5110.5 1003.37  5121.7 1003.07    5205 1004.97  5264.9 1007.71
#Mann= 4 ,-1 , 0
  4660.7     .12       0  4690.3     .05       0    4977     .03       0
    4981     .05       0
Bank Sta=4977,4981
XS Rating Curve= 0 ,0
Exp/Cntr=0.3,0.1

Type RM Length L Ch R = 1 ,19598   ,388,388,388
BEGIN DESCRIPTION:
SANDY CREEK 37.0
END DESCRIPTION:
XS GIS Cut Line= 3
      2877805.69     10243803.12      2877219.25       10243612.
      2876905.72     10243503.12
#Sta/Elev= 30
  4383.2 1008.07  4393.7 1007.83  4399.2 1006.95  4431.1 1005.12  4461.4 1004.04
  4493.6 1002.83  4551.5 1000.84    4564  998.57  4572.5 1000.57  4590.6 1002.97
  4687.1 1003.58  4691.6  1003.1  4849.2  1002.2  4930.1 1001.11  4972.2   998.7
  4978.9  997.17  4984.1  997.34  4997.2  995.36  4997.5  994.86    5001  994.86
  5001.2  995.36  5024.9  996.48  5041.6  998.28  5067.3  998.42  5134.9 1001.09
  5197.2 1004.56  5215.5 1004.77  5228.3 1006.13    5279 1008.14  5331.9  1011.5
#Mann= 7 ,-1 , 0
  4383.2     .05       0  4461.4     .12       0  4493.6     .05       0
  4687.1     .12       0  4849.2     .05       0  4997.2     .03       0
  5001.2     .05       0
Bank Sta=4997.2,5001.2
XS Rating Curve= 0 ,0
Exp/Cntr=0.3,0.1