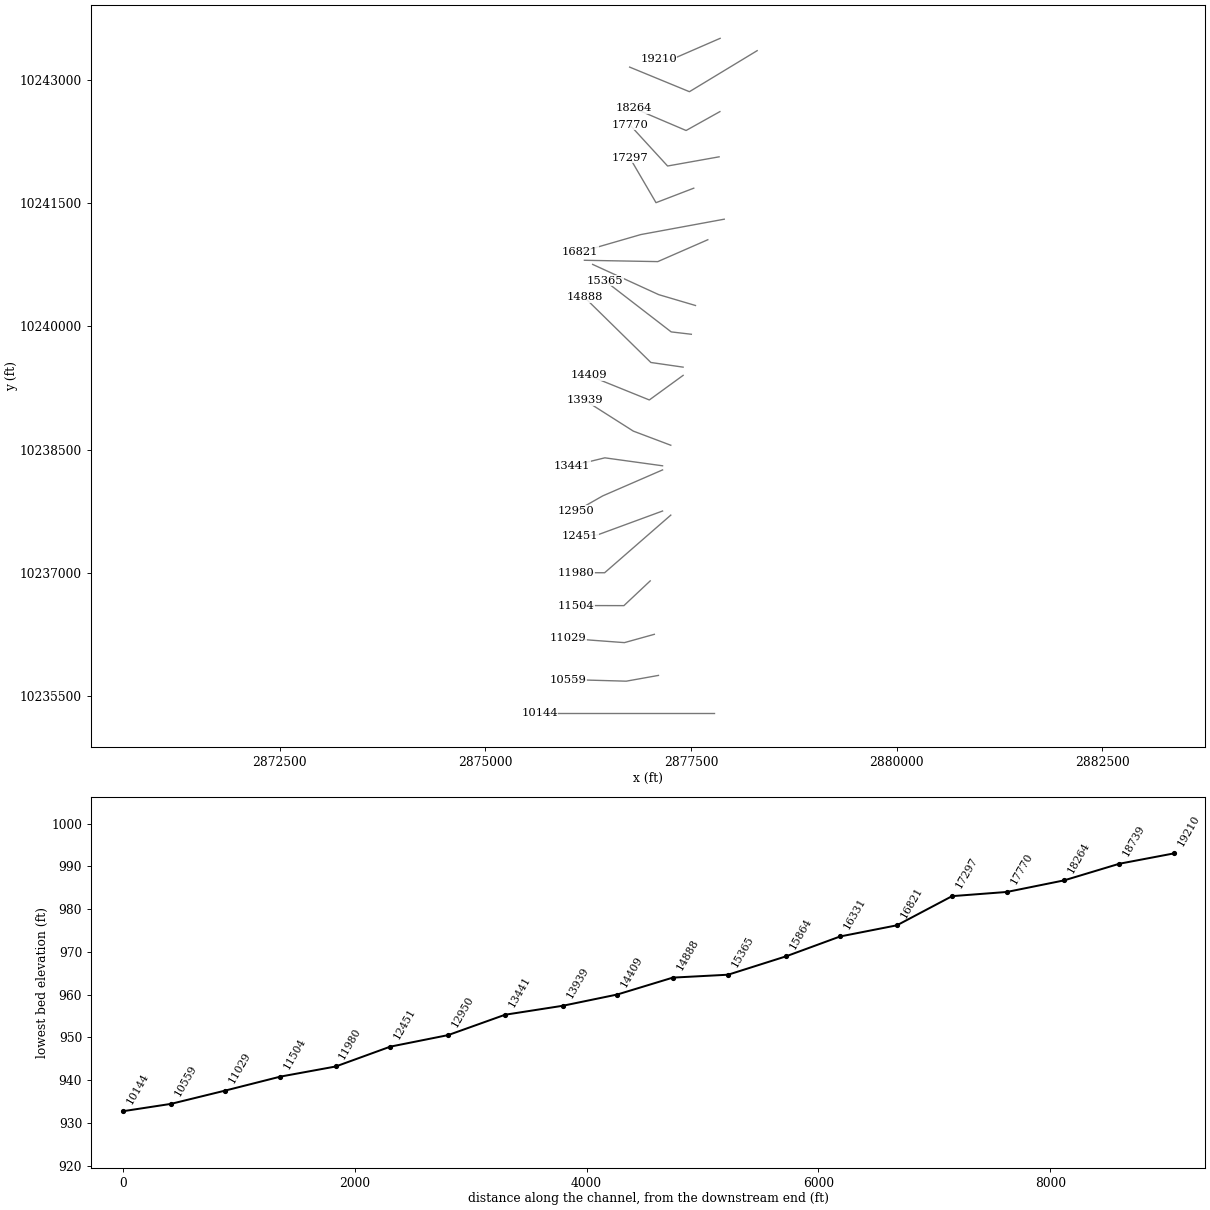
HEC-RAS study SANDY CREEK.prj: SANDY CREEK Base Level Engineering

--- SANDY CREEK.g01 (geometry) --- (continued)

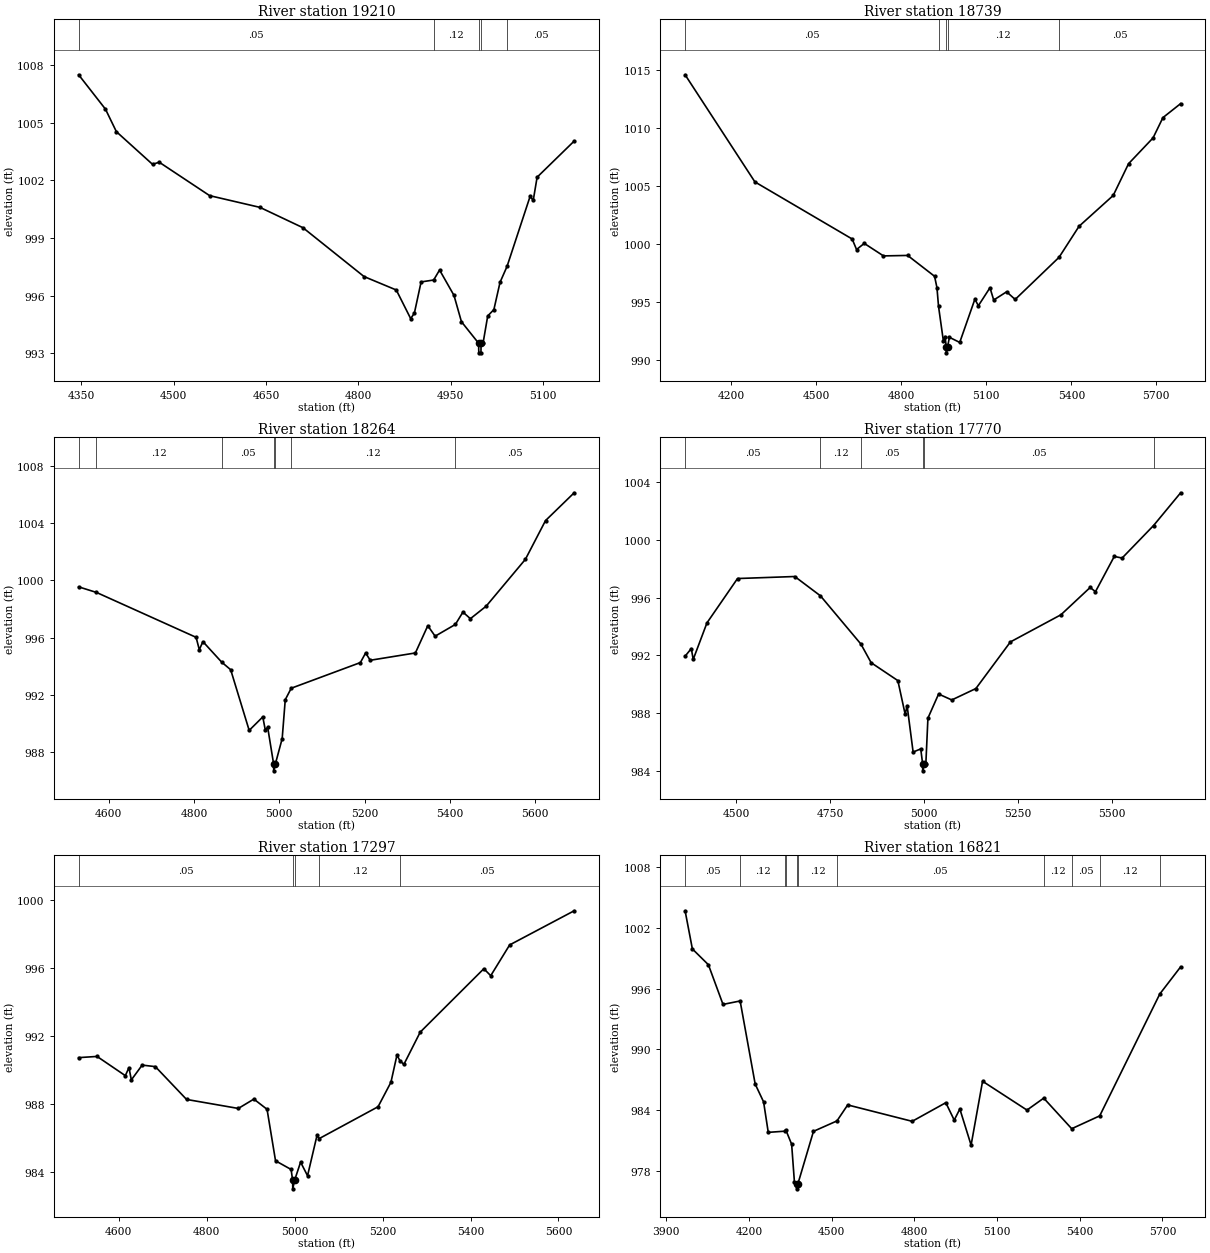
Type RM Length L Ch R = 1 ,19210   ,471,471,471
BEGIN DESCRIPTION:
SANDY CREEK 36.0
END DESCRIPTION:
XS GIS Cut Line= 3
      2877855.69     10243503.11      2877255.75       10243242.
      2877105.66     10243253.11
#Sta/Elev= 30
  4345.7 1007.49  4389.3  1005.7    4407 1004.53  4465.7 1002.83  4476.6 1002.94
  4558.5  1001.2  4640.2 1000.59  4710.1  999.53  4809.2  996.99  4861.6  996.29
    4885   994.8    4891  995.09  4901.9  996.71  4922.3  996.81  4931.9  997.33
  4955.3  996.01  4967.4  994.64  4995.3  993.52  4995.6  993.02  4999.1  993.02
  4999.3  993.52  5002.5  993.52  5010.1  994.94  5020.1  995.27  5030.1  996.69
  5041.5  997.52    5079 1001.17    5084 1000.95  5090.3 1002.16  5150.5 1004.04
#Mann= 5 ,-1 , 0
  4345.7     .05       0  4922.3     .12       0  4995.3     .07       0
  4999.3     .12       0  5041.5     .05       0
Bank Sta=4995.3,4999.3
XS Rating Curve= 0 ,0
Exp/Cntr=0.3,0.1

Type RM Length L Ch R = 1 ,18739   ,475,475,475
BEGIN DESCRIPTION:
SANDY CREEK 35.0
END DESCRIPTION:
XS GIS Cut Line= 3
      2878305.69     10243353.12      2877482.25       10242854.
      2876755.71      10243153.1
#Sta/Elev= 30
  4037.1 1014.61  4283.4 1005.36  4626.6 1000.43  4642.1  999.52  4669.3 1000.05
  4737.1  998.97  4822.4  999.01  4917.4  997.21  4925.8  996.23  4931.4  994.61
  4948.4  991.64  4954.3  992.01  4958.8   991.1  4959.1   990.6  4963.1   991.1
  4969.8  991.94  5006.2   991.5  5059.6  995.23    5072  994.67  5112.9  996.22
  5126.1  995.16  5171.6  995.87  5201.8  995.21  5356.7  998.85  5427.3 1001.53
  5547.8 1004.19  5601.9 1006.93  5688.4 1009.16  5723.2 1010.91  5785.7 1012.12
#Mann= 5 ,-1 , 0
  4037.1     .05       0  4931.4     .12       0  4958.8     .07       0
  4963.1     .12       0  5356.7     .05       0
Bank Sta=4958.8,4963.1
XS Rating Curve= 0 ,0
Exp/Cntr=0.3,0.1

Type RM Length L Ch R = 1 ,18264   ,494,494,494
BEGIN DESCRIPTION:
SANDY CREEK 34.0
END DESCRIPTION:
XS GIS Cut Line= 3
      2877852.71     10242611.71      2877441.75       10242382.
      2876805.72      10242653.1
#Sta/Elev= 30
  4529.2  999.55  4571.1  999.16  4804.7  996.03  4812.2  995.17  4820.7  995.73
  4864.7   994.3  4885.8  993.77  4929.2  989.54  4961.1  990.48  4966.9  989.58
  4972.6  989.75  4986.4  987.22  4986.7  986.72  4990.8  987.22  5006.6  988.97
  5013.8  991.68  5027.8  992.48    5190  994.27  5202.3  994.94  5213.1  994.43
    5319  994.94  5348.1  996.84  5365.3  996.11  5412.8  996.93  5430.5  997.79
    5448  997.33  5484.9   998.2    5577 1001.47  5624.2 1004.17  5691.4 1006.11
#Mann= 7 ,-1 , 0
  4529.2     .05       0  4571.1     .12       0  4864.7     .05       0
  4986.4     .05       0  4990.8     .05       0  5027.8     .12       0
  5412.8     .05       0
Bank Sta=4986.4,4990.8
XS Rating Curve= 0 ,0
Exp/Cntr=0.3,0.1

Type RM Length L Ch R = 1 ,17770   ,473,473,473
BEGIN DESCRIPTION:
SANDY CREEK 33.0
END DESCRIPTION:
XS GIS Cut Line= 3
      2877842.96     10242061.71      2877216.75       10241950.
       2876755.7     10242453.09
#Sta/Elev= 30
  4363.9  991.95  4380.4  992.48  4385.5  991.73  4422.1  994.26  4503.4  997.33
  4655.7  997.47  4724.1  996.13  4831.7  992.79  4858.9   991.5    4930  990.26
  4949.5  987.92  4954.6  988.53  4970.6  985.31  4990.9  985.53  4995.8  984.51
  4996.1  984.01  5000.2  984.51  5004.5  984.51    5010  987.66  5038.4  989.33
  5073.5  988.92  5137.6  989.71  5229.5  992.94  5363.9  994.82  5441.6  996.71
  5455.8  996.42  5505.8  998.86  5526.7  998.75  5610.3    1001  5682.4 1003.27
#Mann= 6 ,-1 , 0
  4363.9     .05       0  4724.1     .12       0  4831.7     .05       0
  4995.8     .03       0  5000.2     .05       0  5610.3     .12       0
Bank Sta=4995.8,5000.2
XS Rating Curve= 0 ,0
Exp/Cntr=0.3,0.1

Type RM Length L Ch R = 1 ,17297   ,476,476,476
BEGIN DESCRIPTION:
SANDY CREEK 32.0
END DESCRIPTION:
XS GIS Cut Line= 3
      2877534.82     10241680.24        2877076.       10241504.
      2876755.69      10242053.1
#Sta/Elev= 30
  4508.5  990.75  4550.4  990.82  4614.7  989.69    4623  990.16  4628.4  989.44
    4653  990.31    4683  990.22    4754  988.29  4871.7  987.76  4907.1  988.31
  4937.1  987.71  4956.4  984.68  4991.8  984.17  4995.3  983.53  4995.6  983.03
  4999.7  983.53  5013.4   984.6  5029.2   983.8  5050.7  986.17    5056  985.99
  5189.6  987.86  5218.9   989.3  5232.6   990.9  5239.1  990.58  5248.3  990.35
  5285.5  992.25  5430.2  995.98  5445.9  995.57  5488.9  997.38  5635.7  999.39
#Mann= 5 ,-1 , 0
  4508.5     .05       0  4995.3     .05       0  4999.7     .05       0
    5056     .12       0  5239.1     .05       0
Bank Sta=4995.3,4999.7
XS Rating Curve= 0 ,0
Exp/Cntr=0.3,0.1

Type RM Length L Ch R = 1 ,16821   ,490,490,490
BEGIN DESCRIPTION:
SANDY CREEK 31.0
END DESCRIPTION:
XS GIS Cut Line= 3
      2877905.64      10241303.1      2876891.25       10241116.
      2876155.64      10240903.1
#Sta/Elev= 30
  3968.5 1003.68  3994.9  999.91    4053  998.35    4106  994.43  4168.1  994.77
  4222.7  986.56  4253.2   984.8  4270.1  981.79  4332.3  981.91  4333.6  982.04
  4354.9  980.62    4365  976.89  4372.8  976.71  4373.1  976.21  4377.7  976.71
  4434.1  981.89  4519.3  982.92  4558.2   984.5  4792.1  982.88  4914.1  984.72
  4944.6     983    4965   984.1  5005.8  980.53  5047.4  986.84  5208.5  983.99
  5269.2  985.17  5370.7  982.15  5472.3  983.42  5690.2  995.46  5765.8  998.14
#Mann= 11 ,-1 , 0
  3968.5     .05       0  4168.1     .12       0  4332.3     .05       0
  4333.6     .12       0  4372.8     .05       0  4377.7     .12       0
  4519.3     .05       0  5269.2     .12       0  5370.7     .05       0
  5472.3     .12       0  5690.2     .05       0
Bank Sta=4372.8,4377.7
XS Rating Curve= 0 ,0
Exp/Cntr=0.3,0.1

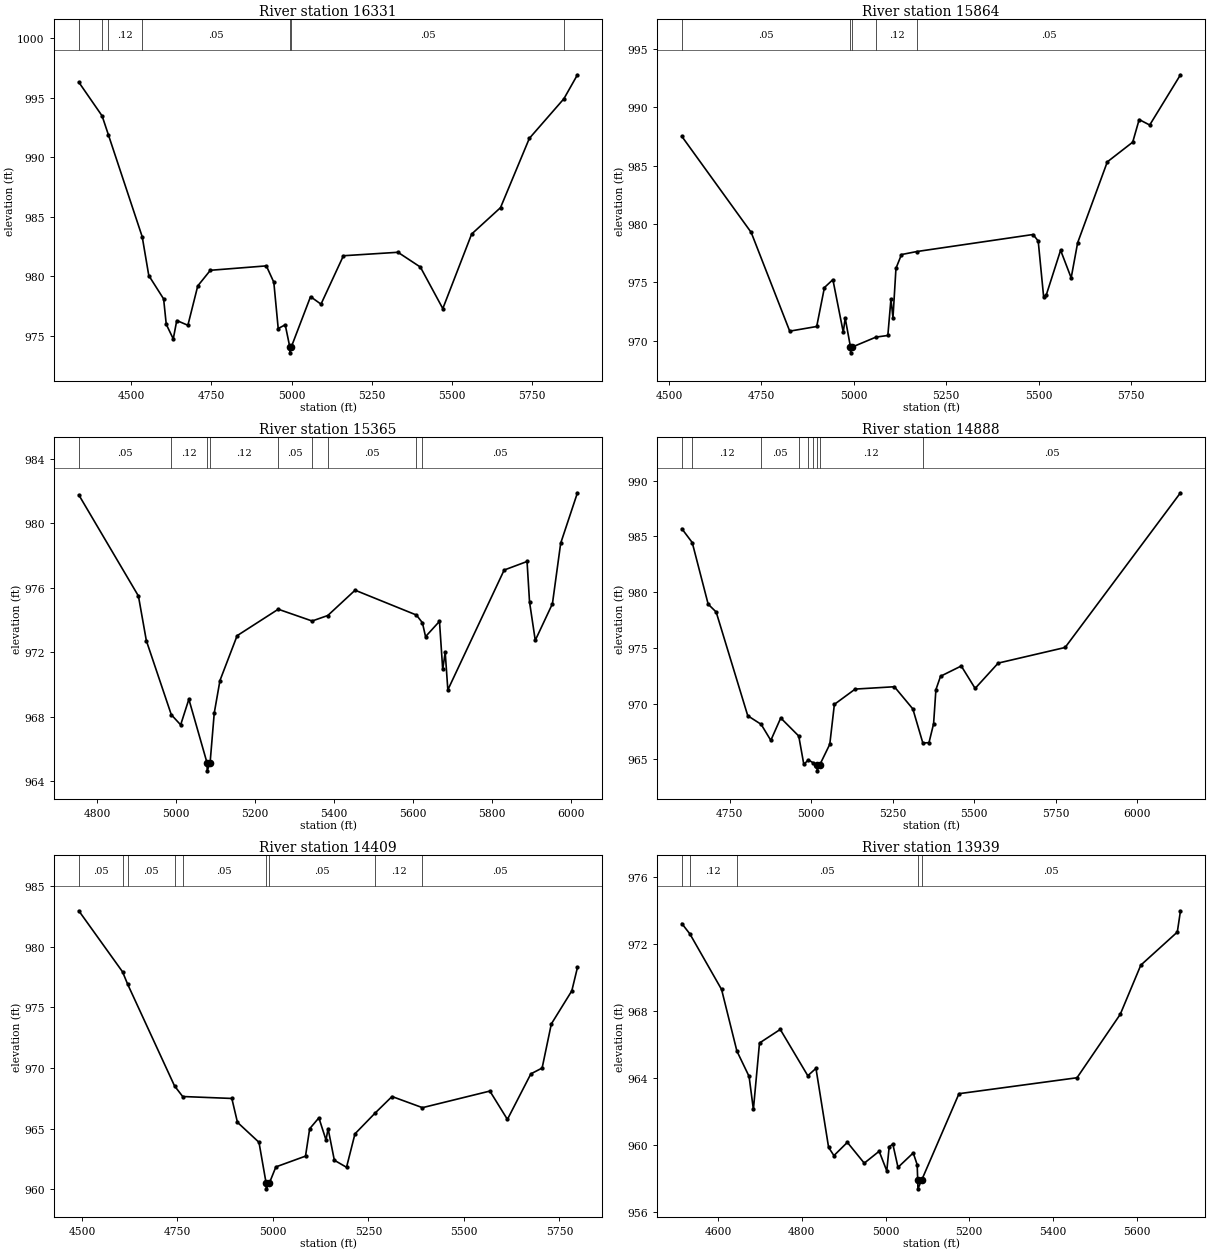
Type RM Length L Ch R = 1 ,16331   ,467,467,467
BEGIN DESCRIPTION:
SANDY CREEK 30.0
END DESCRIPTION:
XS GIS Cut Line= 3
      2877705.73     10241053.13       2877097.5       10240787.
      2876205.65     10240803.11
#Sta/Elev= 30
  4336.1  996.29  4408.9  993.46  4428.2   991.9    4534  983.33  4554.5  980.08
  4600.8  978.12    4609  975.99  4630.9  974.77  4641.8  976.31  4676.5  975.91
  4707.3  979.21  4746.6  980.52  4921.3  980.89  4944.6  979.52  4958.3  975.64
  4980.2  975.95  4994.4   974.1  4994.8   973.6  4999.3   974.1  5059.2  978.31
  5091.8  977.68  5161.8  981.74  5331.9  982.03  5401.9  980.79  5471.9  977.31
  5561.9  983.56  5651.9  985.77  5741.9  991.58  5849.7   994.9    5892  996.91
#Mann= 7 ,-1 , 0
  4336.1     .12       0  4408.9     .05       0  4428.2     .12       0
    4534     .05       0  4994.4     .05       0  4999.3     .05       0
  5849.7     .12       0
Bank Sta=4994.4,4999.3
XS Rating Curve= 0 ,0
Exp/Cntr=0.3,0.1

Type RM Length L Ch R = 1 ,15864   ,499,499,499
BEGIN DESCRIPTION:
SANDY CREEK 29.0
END DESCRIPTION:
XS GIS Cut Line= 3
      2877555.71      10240253.1       2877109.5       10240385.
      2876305.68     10240753.11
#Sta/Elev= 30
  4534.7  987.52  4722.4  979.28  4826.7  970.81  4899.7  971.21  4920.6  974.55
  4943.5  975.23  4971.6  970.72  4976.8  971.93  4991.1  969.45  4991.4  968.95
  4996.1  969.45  5060.1   970.3  5092.2  970.44  5100.6  973.55  5106.1  971.96
  5114.2   976.2  5129.1  977.38  5170.9  977.64  5485.2   979.1  5499.1  978.54
  5513.7  973.78  5521.1  973.93  5559.7  977.75  5588.3  975.38  5605.8  978.39
  5686.1  985.33  5754.8  987.02  5772.3  988.96  5800.8  988.49  5884.1   992.8
#Mann= 5 ,-1 , 0
  4534.7     .05       0  4991.1     .05       0  4996.1     .05       0
  5060.1     .12       0  5170.9     .05       0
Bank Sta=4991.1,4996.1
XS Rating Curve= 0 ,0
Exp/Cntr=0.3,0.1

Type RM Length L Ch R = 1 ,15365   ,477,477,477
BEGIN DESCRIPTION:
SANDY CREEK 28.0
END DESCRIPTION:
XS GIS Cut Line= 3
       2877505.7     10239903.11       2877260.5       10239932.
       2876455.7      10240553.1
#Sta/Elev= 30
  4753.1  981.77  4904.2   975.5  4924.3  972.73  4987.5  968.14  5011.2  967.51
    5032   969.1    5078  965.16  5078.5  964.66  5085.8  965.16  5096.3  968.24
  5110.8  970.26  5154.3  973.04  5258.5  974.68  5344.3  973.95    5384  974.29
  5453.2  975.86  5608.6  974.32  5623.8  973.84  5631.7  972.98    5667  973.93
  5675.2  970.95  5681.5  972.01  5688.2  969.68  5830.9  977.11  5888.9  977.64
  5895.2  975.13  5909.7  972.75  5953.2  975.02  5974.1  978.77  6016.6   981.9
#Mann= 9 ,-1 , 0
  4753.1     .05       0  4987.5     .12       0    5078     .07       0
  5085.8     .12       0  5258.5     .05       0  5344.3     .12       0
    5384     .05       0  5608.6     .12       0  5623.8     .05       0
Bank Sta=5078,5085.8
XS Rating Curve= 0 ,0
Exp/Cntr=0.3,0.1

Type RM Length L Ch R = 1 ,14888   ,479,479,479
BEGIN DESCRIPTION:
SANDY CREEK 27.0
END DESCRIPTION:
XS GIS Cut Line= 3
       2877405.7     10239503.11       2877013.5       10239560.
      2876205.67     10240353.13
#Sta/Elev= 30
  4603.7  985.69  4635.6  984.45  4684.5  978.92    4709  978.22  4805.8  968.92
  4846.8  968.15  4876.5  966.71  4906.9  968.72  4962.1   967.1  4977.6  964.56
  4991.6  964.96  5006.1   964.7    5018  964.48  5018.5  963.98  5025.9  964.48
  5057.2  966.36  5071.3  969.94  5135.1  971.31  5255.2  971.52  5311.8  969.53
  5342.5  966.47  5361.3  966.51  5375.4   968.2  5382.5  971.26  5396.7  972.46
  5460.2  973.38  5502.7  971.37  5573.4  973.64  5778.5  975.04  6132.1  988.91
#Mann= 9 ,-1 , 0
  4603.7     .05       0  4635.6     .12       0  4846.8     .05       0
  4962.1     .12       0  4991.6     .05       0  5006.1     .12       0
    5018     .05       0  5025.9     .12       0  5342.5     .05       0
Bank Sta=5018,5025.9
XS Rating Curve= 0 ,0
Exp/Cntr=0.3,0.1

Type RM Length L Ch R = 1 ,14409   ,470,470,470
BEGIN DESCRIPTION:
SANDY CREEK 26.0
END DESCRIPTION:
XS GIS Cut Line= 3
      2877405.71     10239403.13      2876994.75       10239104.
      2876255.68     10239403.11
#Sta/Elev= 30
  4491.7  982.98  4606.3  977.94  4619.9   976.9  4742.3  968.53  4763.7  967.65
  4892.4  967.49  4907.1  965.52  4963.5  963.87    4982  960.53  4982.5  960.03
    4991  960.53  5007.7  961.84  5085.3  962.73  5096.2  964.99  5120.3  965.89
    5139  964.06  5144.4     965  5160.8  962.39  5192.7  961.81  5214.8  964.57
  5267.1  966.27  5311.8  967.65  5391.5  966.73    5568   968.1  5613.9  965.76
  5675.3  969.52  5704.8     970  5728.9  973.64  5782.5  976.37  5797.3   978.3
#Mann= 9 ,-1 , 0
  4491.7     .05       0  4606.3     .12       0  4619.9     .05       0
  4742.3     .12       0  4763.7     .05       0    4982     .05       0
    4991     .05       0  5267.1     .12       0  5391.5     .05       0
Bank Sta=4982,4991
XS Rating Curve= 0 ,0
Exp/Cntr=0.3,0.1

Type RM Length L Ch R = 1 ,13939   ,498,498,498
BEGIN DESCRIPTION:
SANDY CREEK 25.0
END DESCRIPTION:
XS GIS Cut Line= 3
      2877255.69     10238553.11      2876800.25       10238725.
      2876205.69     10239103.11
#Sta/Elev= 30
  4513.2  973.21  4532.5  972.59  4608.2  969.28  4644.8  965.61  4673.9   964.1
  4684.2  962.13  4698.8  966.09  4748.4   966.9  4814.2  964.14  4833.7  964.58
  4863.9  959.87  4876.6  959.38  4908.7  960.17  4949.1  958.93  4984.7  959.64
  5002.9  958.47  5008.6   959.9  5017.3  960.07  5029.7  958.68  5066.1  959.54
  5075.5  958.84  5076.8   957.9  5077.3   957.4  5085.9   957.9  5175.4  963.07
  5457.4  964.02  5560.7   967.8  5609.8  970.73    5697   972.7  5704.6  973.97
#Mann= 5 ,-1 , 0
  4513.2     .05       0  4532.5     .12       0  4644.8     .05       0
  5076.8     .03       0  5085.9     .05       0
Bank Sta=5076.8,5085.9
XS Rating Curve= 0 ,0
Exp/Cntr=0.3,0.1

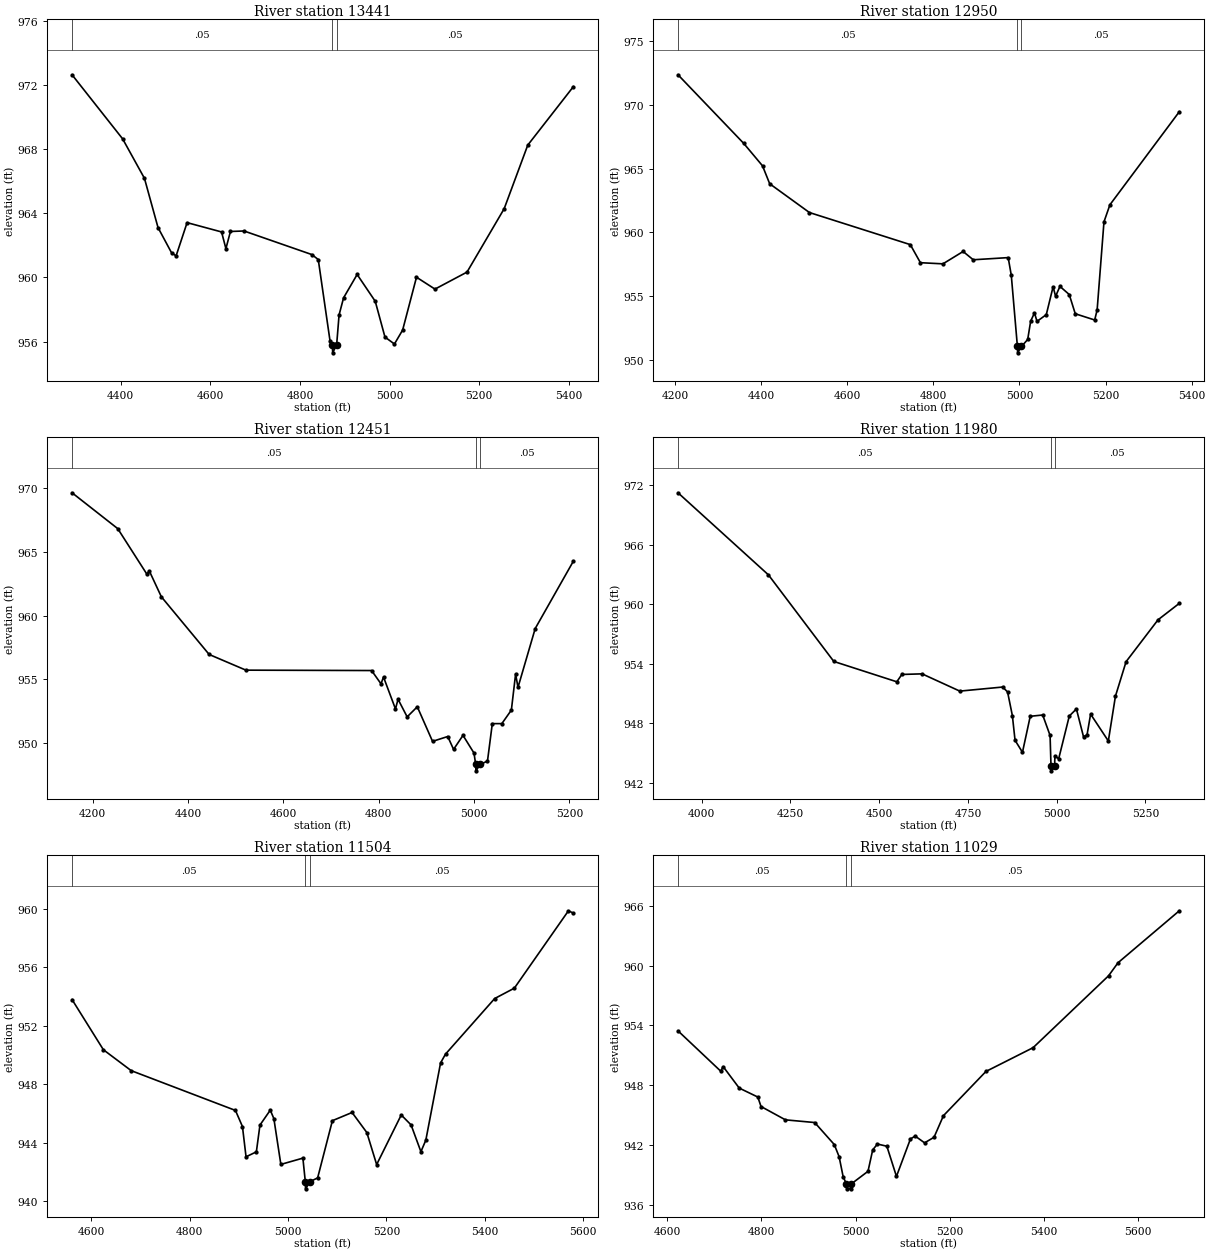
Type RM Length L Ch R = 1 ,13441   ,491,491,491
BEGIN DESCRIPTION:
SANDY CREEK 24.0
END DESCRIPTION:
XS GIS Cut Line= 3
      2877155.64     10238303.12        2876454.       10238400.
      2876055.71     10238303.12
#Sta/Elev= 30
  4291.7  972.62  4404.5  968.63  4453.2  966.17  4483.5   963.1  4513.7  961.53
  4523.8  961.34  4548.3  963.41  4625.2  962.83  4634.9  961.79    4645  962.86
  4675.3  962.89  4826.7  961.42  4840.9  961.11  4867.1  956.05  4872.5   955.8
    4873   955.3  4881.9   955.8  4887.3  957.66  4897.4  958.73  4927.6  960.18
    4968  958.51  4989.7  956.28  5010.8  955.85  5029.1  956.72    5060  960.01
  5101.2  959.27  5172.7  960.33  5255.6  964.28  5308.2  968.24  5409.9  971.88
#Mann= 3 ,-1 , 0
  4291.7     .05       0  4872.5     .03       0  4881.9     .05       0
Bank Sta=4872.5,4881.9
XS Rating Curve= 0 ,0
Exp/Cntr=0.3,0.1

Type RM Length L Ch R = 1 ,12950   ,499,499,499
BEGIN DESCRIPTION:
SANDY CREEK 23.0
END DESCRIPTION:
XS GIS Cut Line= 3
      2877155.73     10238253.13      2876428.25       10237937.
      2876105.68     10237753.11
#Sta/Elev= 30
  4206.8  972.38  4359.5  966.99  4403.1  965.23  4419.8  963.82  4512.1  961.56
  4746.4  959.04  4769.9  957.62  4822.2  957.53  4869.1   958.5  4892.6  957.85
  4973.8  958.02    4981  956.63  4995.2  951.04  4995.7  950.54  5004.7  951.04
  5019.1  951.59    5026  953.03  5034.9  953.68  5040.7  953.01  5062.3  953.54
  5078.1  955.73  5083.9  954.98    5094  955.76  5115.6  955.12  5129.6  953.61
  5174.7  953.12  5180.4  953.91  5196.3  960.83  5210.1  962.17  5371.3  969.48
#Mann= 3 ,-1 , 0
  4206.8     .05       0  4995.2     .05       0  5004.7     .05       0
Bank Sta=4995.2,5004.7
XS Rating Curve= 0 ,0
Exp/Cntr=0.3,0.1

Type RM Length L Ch R = 1 ,12451   ,471,471,471
BEGIN DESCRIPTION:
SANDY CREEK 22.0
END DESCRIPTION:
XS GIS Cut Line= 3
      2877155.67     10237753.11        2876364.       10237462.
      2876155.69     10237453.11
#Sta/Elev= 30
  4156.5  969.63  4252.4  966.82  4313.4  963.26  4318.7   963.5  4343.9  961.48
  4444.2  956.96  4521.4  955.73  4785.1   955.7  4804.8  954.66  4810.1  955.19
  4835.2  952.69  4840.6  953.45  4859.7  952.07    4881  952.86    4913  950.15
  4944.9  950.53  4957.1  949.52  4976.9  950.62    5000  949.23  5003.5  948.34
    5004  947.84  5013.1  948.34  5028.3  948.61  5038.4  951.54  5058.4  951.54
  5078.4   952.6  5087.3  955.43  5092.3  954.38  5128.4  958.99  5208.5  964.27
#Mann= 3 ,-1 , 0
  4156.5     .05       0  5003.5     .05       0  5013.1     .05       0
Bank Sta=5003.5,5013.1
XS Rating Curve= 0 ,0
Exp/Cntr=0.3,0.1

Type RM Length L Ch R = 1 ,11980   ,476,476,476
BEGIN DESCRIPTION:
SANDY CREEK 21.0
END DESCRIPTION:
XS GIS Cut Line= 3
      2877255.69     10237703.11       2876451.5       10237002.
       2876105.7     10237003.11
#Sta/Elev= 30
  3933.1  971.24    4188  962.96  4372.2  954.23  4549.7  952.18  4563.9  952.92
  4620.9  952.98  4727.2  951.24  4847.8  951.65  4861.8  951.16  4875.3  948.78
  4882.9  946.28  4903.8  945.07  4925.7   948.7  4960.8  948.83  4981.6  946.77
  4984.2   943.7  4984.7   943.2  4994.3   943.7  4995.3  944.71  5005.8  944.41
  5035.8  948.73  5055.8  949.44  5075.8  946.64  5085.8  946.83  5095.8  948.92
  5145.8  946.21  5165.8  950.73  5195.8  954.21  5285.8  958.43  5345.8  960.09
#Mann= 3 ,-1 , 0
  3933.1     .05       0  4984.2     .03       0  4994.3     .05       0
Bank Sta=4984.2,4994.3
XS Rating Curve= 0 ,0
Exp/Cntr=0.3,0.1

Type RM Length L Ch R = 1 ,11504   ,475,475,475
BEGIN DESCRIPTION:
SANDY CREEK 20.0
END DESCRIPTION:
XS GIS Cut Line= 3
      2877005.65     10236903.08      2876685.75       10236602.
      2876105.65     10236603.11
#Sta/Elev= 30
  4560.7  953.78  4624.4  950.35    4681  948.92    4893   946.2  4907.2   945.1
  4914.5  943.03  4935.5  943.37  4942.8   945.2  4963.8  946.22  4971.1  945.64
  4985.3  942.51  5030.1  942.94    5035  941.34  5035.5  940.84  5045.1  941.34
  5060.1  941.59  5090.1   945.5  5130.1  946.06  5160.1  944.69  5180.1   942.5
  5230.1  945.89  5250.1  945.21  5270.1  943.38  5280.1  944.17  5310.1  949.45
  5320.1  950.05  5420.1  953.85  5460.1  954.56  5570.1  959.85  5580.1  959.69
#Mann= 3 ,-1 , 0
  4560.7     .05       0    5035     .03       0  5045.1     .05       0
Bank Sta=5035,5045.1
XS Rating Curve= 0 ,0
Exp/Cntr=0.3,0.1

Type RM Length L Ch R = 1 ,11029   ,470,470,470
BEGIN DESCRIPTION:
SANDY CREEK 19.0
END DESCRIPTION:
XS GIS Cut Line= 3
      2877055.71     10236253.12        2876692.       10236152.
       2876005.7     10236203.11
#Sta/Elev= 30
  4622.5  953.45  4713.3   949.4  4718.5  949.86  4752.7   947.7  4792.2   946.8
    4799  945.85  4850.9  944.51  4913.1  944.24  4954.7  942.03    4965  940.81
  4973.7  938.77  4980.6  938.08  4981.1  937.58  4990.5  937.58    4991  938.08
  5026.4  939.34  5036.4  941.49  5046.4  942.08  5066.5  941.86  5086.9  938.83
  5116.6  942.59  5126.7  942.88  5146.7   942.2  5166.8  942.76  5186.8  944.93
  5277.1  949.37  5377.4  951.76  5537.8  958.98  5557.9  960.29  5688.2  965.51
#Mann= 3 ,-1 , 0
  4622.5     .05       0  4980.6     .03       0    4991     .05       0
Bank Sta=4980.6,4991
XS Rating Curve= 0 ,0
Exp/Cntr=0.3,0.1

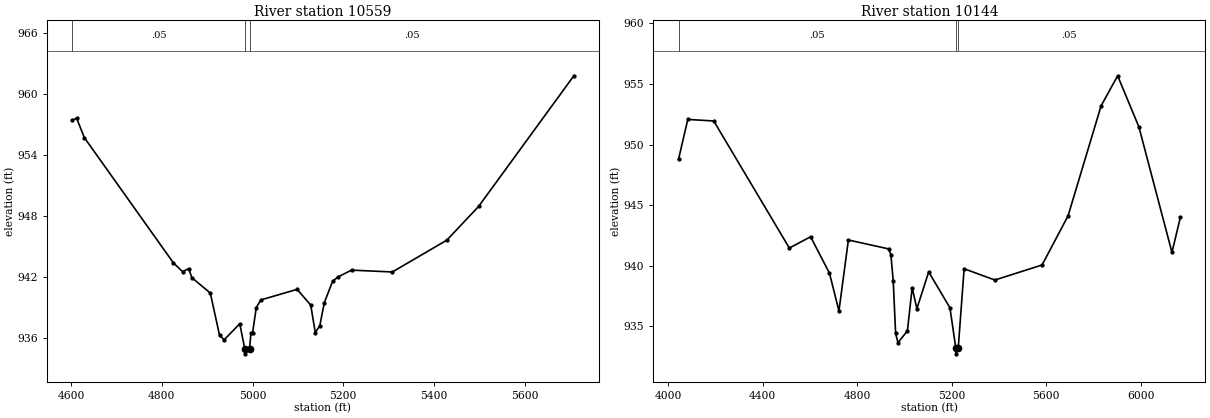
Type RM Length L Ch R = 1 ,10559   ,415,415,415
BEGIN DESCRIPTION:
SANDY CREEK 18.0
END DESCRIPTION:
XS GIS Cut Line= 3
      2877105.67     10235753.11        2876714.       10235683.
      2876005.69     10235703.11
#Sta/Elev= 30
  4602.1  957.41  4612.2  957.63    4629  955.73  4825.6   943.4  4845.9  942.54
  4859.3  942.84  4866.2  941.95  4906.9  940.44  4927.2   936.3  4937.3  935.83
  4971.9  937.42  4982.9  934.96  4983.4  934.46  4993.4  934.96  4996.6  936.49
    5000  936.49  5008.3  939.01  5018.3  939.76  5098.4   940.8  5128.4  939.25
  5138.4  936.55  5148.4  937.24  5158.4   939.5  5176.7   941.6  5188.4  942.02
  5218.4  942.69  5308.4  942.51  5428.5  945.64  5498.5  948.95  5708.6   961.8
#Mann= 3 ,-1 , 0
  4602.1     .05       0  4982.9     .05       0  4993.4     .05       0
Bank Sta=4982.9,4993.4
XS Rating Curve= 0 ,0
Exp/Cntr=0.3,0.1

Type RM Length L Ch R = 1 ,10144   ,326,326,326
BEGIN DESCRIPTION:
Mapping XS ae5aaec2
END DESCRIPTION:
XS GIS Cut Line= 3
      2877784.75     10235291.33      2876555.61     10235291.33
      2875660.25     10235291.33
#Sta/Elev= 30
  4043.3  948.79  4082.4  952.08  4192.4  951.95  4512.4  941.47  4602.4   942.4
  4682.4  939.39  4722.4  936.28  4762.4  942.13  4932.4   941.4  4942.4  940.93
  4952.4  938.72  4962.4  934.42  4972.4  933.66  5012.4  934.64  5032.4   938.2
  5052.4  936.47  5102.4   939.5  5192.4  936.54  5217.1  933.24  5217.6  932.74
  5227.6  933.24  5252.4  939.76  5382.4  938.83  5582.4  940.07  5692.4  944.12
  5832.4   953.2  5902.4  955.68  5992.4  951.46  6132.4  941.11  6167.8  943.99
#Mann= 3 ,-1 , 0
  4043.3     .05       0  5217.1     .03       0  5227.6     .05       0
Bank Sta=5217.1,5227.6
XS Rating Curve= 0 ,0
Exp/Cntr=0.3,0.1