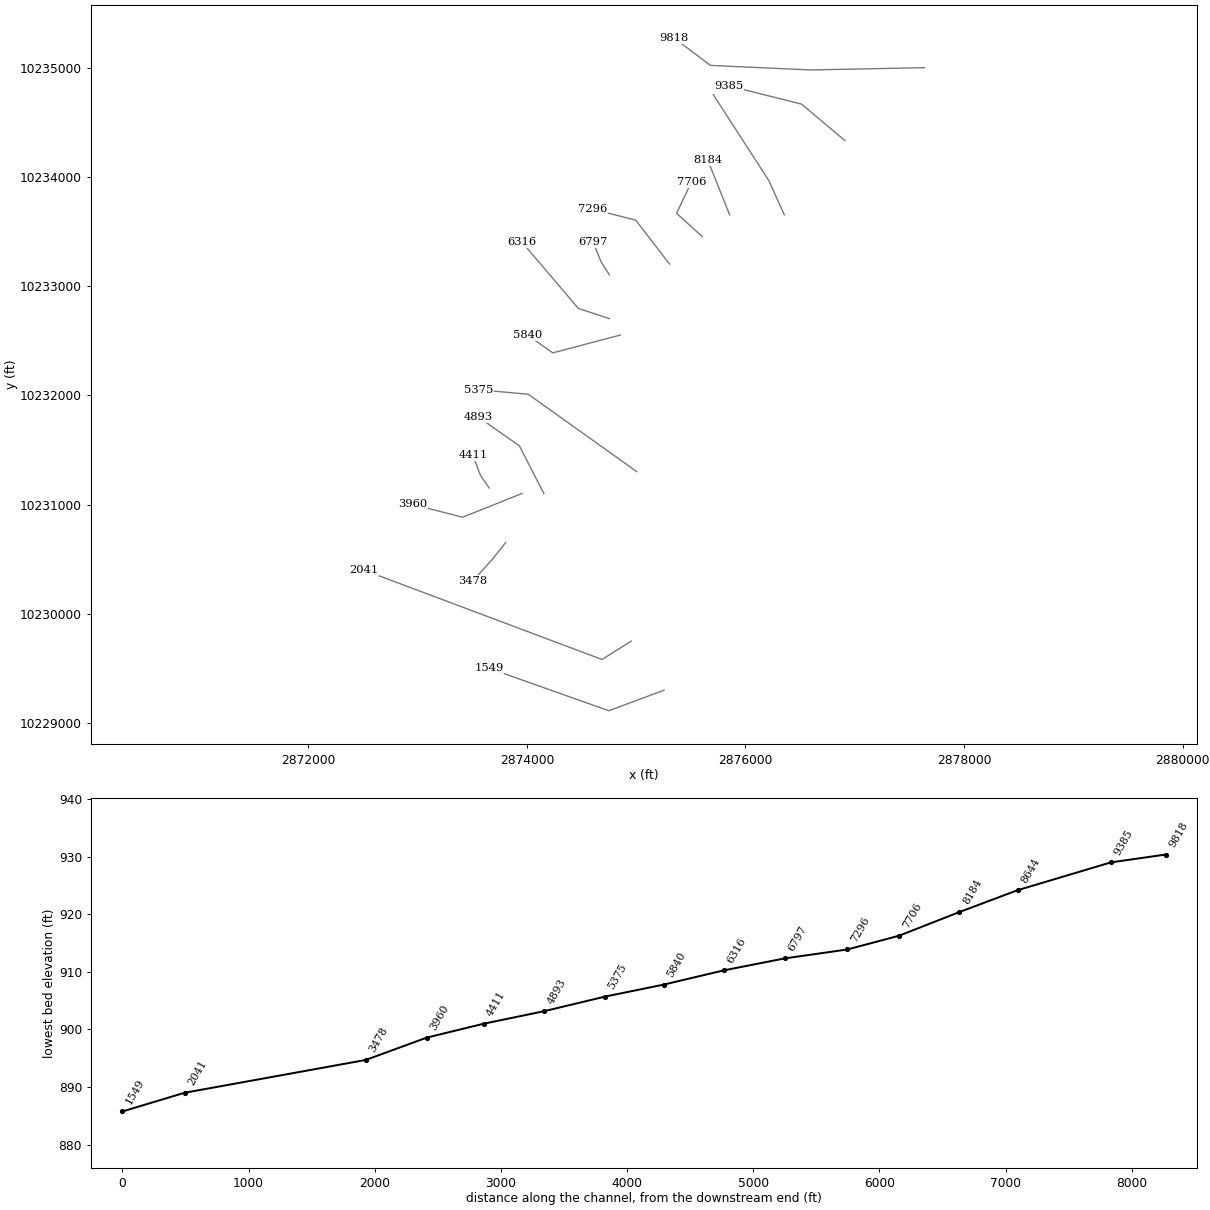
HEC-RAS study SANDY CREEK.prj: SANDY CREEK Base Level Engineering

--- SANDY CREEK.g01 (geometry) --- (continued)

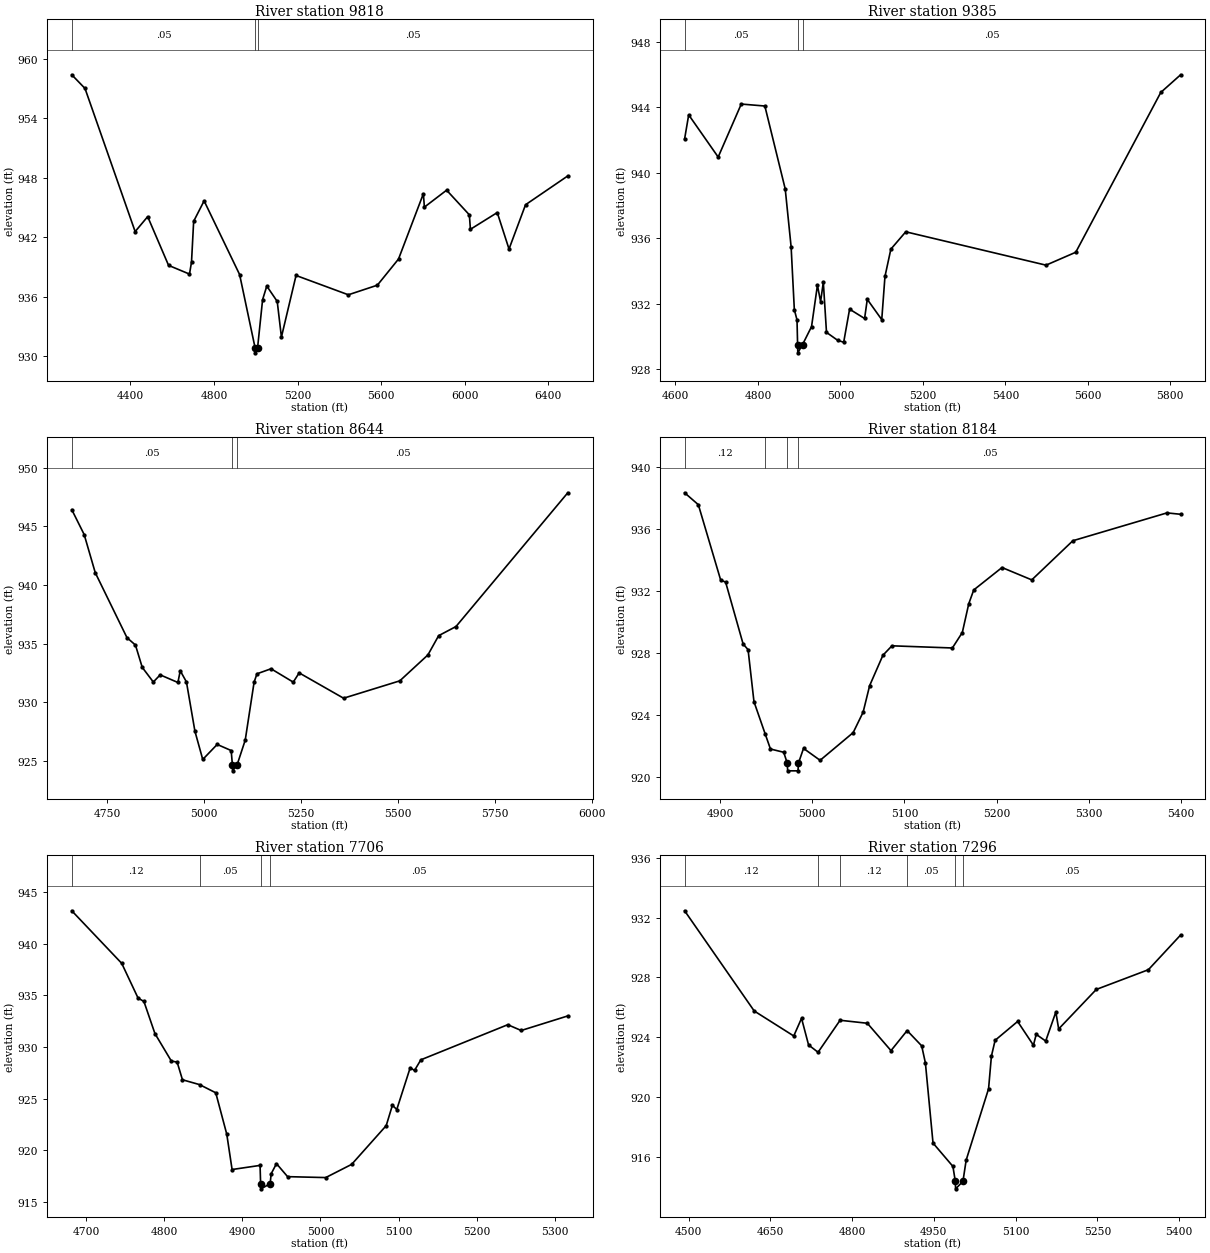
Type RM Length L Ch R = 1 ,9818    ,433,433,433
BEGIN DESCRIPTION:
Mapping XS 619bc3f0
END DESCRIPTION:
XS GIS Cut Line= 4
      2877638.94     10234999.67      2876597.27     10234978.83
      2875680.61      10235020.5      2875348.84     10235269.33
#Sta/Elev= 30
  4119.2  958.41  4182.5  957.03  4422.5  942.58  4482.5  944.09  4582.5  939.17
  4682.6  938.29  4692.3   939.5  4702.6  943.62  4752.6  945.68  4922.6  938.24
  4996.7  930.84  4997.2  930.34  5008.5  930.84  5032.6  935.71  5052.6  937.08
  5102.6  935.53  5122.7  931.93  5192.7  938.15    5443   936.2  5581.9  937.17
  5683.2  939.81  5802.1   946.4  5807.1  945.05  5913.4  946.76  6022.3  944.27
  6027.3  942.81  6155.8   944.5  6212.1  940.82  6291.2  945.29  6493.4   948.2
#Mann= 3 ,-1 , 0
  4119.2     .05       0  4996.7     .05       0  5008.5     .05       0
Bank Sta=4996.7,5008.5
XS Rating Curve= 0 ,0
Exp/Cntr=0.3,0.1

Type RM Length L Ch R = 1 ,9385    ,741,741,741
BEGIN DESCRIPTION:
Mapping XS b08d1f7f
END DESCRIPTION:
XS GIS Cut Line= 3
      2876909.79     10234332.98      2876513.94     10234666.33
      2875849.02     10234832.56
#Sta/Elev= 30
  4622.2  942.07  4632.1  943.54  4703.6  940.96  4759.6   944.2  4816.8  944.08
  4866.2  939.01  4880.5  935.47  4888.3  931.63  4894.8     931  4896.2  929.49
  4896.7  928.99  4908.1  929.49    4930  930.59  4944.3  933.12    4952  932.12
  4958.6  933.31  4966.3  930.24  4993.7  929.75    5008  929.64  5022.3  931.66
  5058.7  931.09  5065.2  932.26  5100.3  931.02  5108.1  933.66  5122.4  935.33
  5158.5  936.39  5498.7  934.35  5570.8  935.14    5777  944.91  5825.1  945.99
#Mann= 3 ,-1 , 0
  4622.2     .05       0  4896.2     .05       0  4908.1     .05       0
Bank Sta=4896.2,4908.1
XS Rating Curve= 0 ,0
Exp/Cntr=0.3,0.1

Type RM Length L Ch R = 1 ,8644    ,460,460,460
BEGIN DESCRIPTION:
SANDY CREEK 14.0
END DESCRIPTION:
XS GIS Cut Line= 3
      2876355.67     10233653.15       2876215.5       10233965.
       2875705.7     10234753.08
#Sta/Elev= 30
  4658.1  946.41  4690.1  944.29  4718.7  941.04  4800.6   935.5  4822.5  934.87
    4840  932.97  4868.6  931.72  4886.3  932.33  4932.1  931.68  4938.1  932.68
  4954.1  931.73    4976  927.53  4996.2  925.12  5033.5   926.4  5069.6  925.88
  5072.8  924.65  5073.3  924.15  5084.8  924.65  5105.9  926.77  5128.8  931.71
  5136.2  932.42  5172.5  932.85  5229.9  931.71  5245.1   932.5  5359.8  930.34
  5504.9  931.82  5577.5  934.03  5605.2  935.67    5650  936.45  5938.6  947.85
#Mann= 3 ,-1 , 0
  4658.1     .05       0  5072.8     .05       0  5084.8     .05       0
Bank Sta=5072.8,5084.8
XS Rating Curve= 0 ,0
Exp/Cntr=0.3,0.1

Type RM Length L Ch R = 1 ,8184    ,478,478,478
BEGIN DESCRIPTION:
SANDY CREEK 13.0
END DESCRIPTION:
XS GIS Cut Line= 3
      2875855.69     10233653.09       2875804.5       10233782.
       2875655.7     10234153.08
#Sta/Elev= 30
  4861.3  938.34  4876.2  937.57  4900.5  932.69  4905.8  932.57  4924.8  928.57
  4930.2   928.2  4936.6  924.84  4948.8  922.75  4954.5  921.78  4968.9  921.57
  4972.7  920.87  4973.2  920.37  4984.4  920.37  4984.9  920.87  4990.4  921.82
  5008.4  921.05  5044.3  922.84  5055.1  924.16  5062.2  925.88  5076.6  927.84
  5086.4  928.45    5152  928.31  5162.8  929.31  5169.8  931.17  5175.2  932.06
  5205.9  933.51  5238.2  932.71  5282.8  935.24    5385  937.04  5399.8  936.95
#Mann= 4 ,-1 , 0
  4861.3     .12       0  4948.8     .05       0  4972.7     .05       0
  4984.9     .05       0
Bank Sta=4972.7,4984.9
XS Rating Curve= 0 ,0
Exp/Cntr=0.3,0.1

Type RM Length L Ch R = 1 ,7706    ,410,410,410
BEGIN DESCRIPTION:
SANDY CREEK 12.0
END DESCRIPTION:
XS GIS Cut Line= 3
       2875605.7      10233453.1      2875370.25       10233667.
      2875505.66     10233953.07
#Sta/Elev= 30
  4681.9  943.18  4745.8  938.09  4766.7  934.73  4774.2   934.4  4788.3  931.29
  4809.3  928.63  4816.7  928.53  4823.5  926.82  4845.4  926.35  4866.1  925.56
  4880.2  921.55    4887  918.13  4922.8  918.53  4923.5  916.76    4924  916.26
  4935.7  916.76    4937  917.72  4943.8   918.7    4958  917.44  5006.8  917.35
    5040  918.63  5084.2  922.38  5092.1  924.35  5097.7  923.94  5114.9  927.99
  5120.4  927.72  5128.5  928.75  5239.7  932.15  5256.9  931.59  5316.5     933
#Mann= 4 ,-1 , 0
  4681.9     .12       0  4845.4     .05       0  4923.5     .03       0
  4935.7     .05       0
Bank Sta=4923.5,4935.7
XS Rating Curve= 0 ,0
Exp/Cntr=0.3,0.1

Type RM Length L Ch R = 1 ,7296    ,499,499,499
BEGIN DESCRIPTION:
SANDY CREEK 11.0
END DESCRIPTION:
XS GIS Cut Line= 3
      2875305.68     10233203.12      2874996.25       10233605.
      2874605.68     10233703.11
#Sta/Elev= 30
  4492.8  932.46  4620.5  925.76    4693  924.09  4707.3  925.27  4720.2  923.49
  4737.6     923    4778  925.14    4828  924.94  4871.4  923.11    4901  924.45
  4927.7  923.43  4934.5  922.29  4948.5  916.93    4985  915.37  4989.4  914.37
  4989.9  913.87  5003.4  914.37  5009.3  915.79  5050.4  920.56  5055.6  922.74
  5062.4   923.8  5103.7  925.06  5132.7  923.47  5137.8   924.2  5155.2  923.75
  5173.8  925.69    5179  924.56    5248   927.2  5343.6  928.52  5402.7  930.84
#Mann= 6 ,-1 , 0
  4492.8     .12       0  4737.6     .05       0    4778     .12       0
    4901     .05       0  4989.4     .05       0  5003.4     .05       0
Bank Sta=4989.4,5003.4
XS Rating Curve= 0 ,0
Exp/Cntr=0.3,0.1

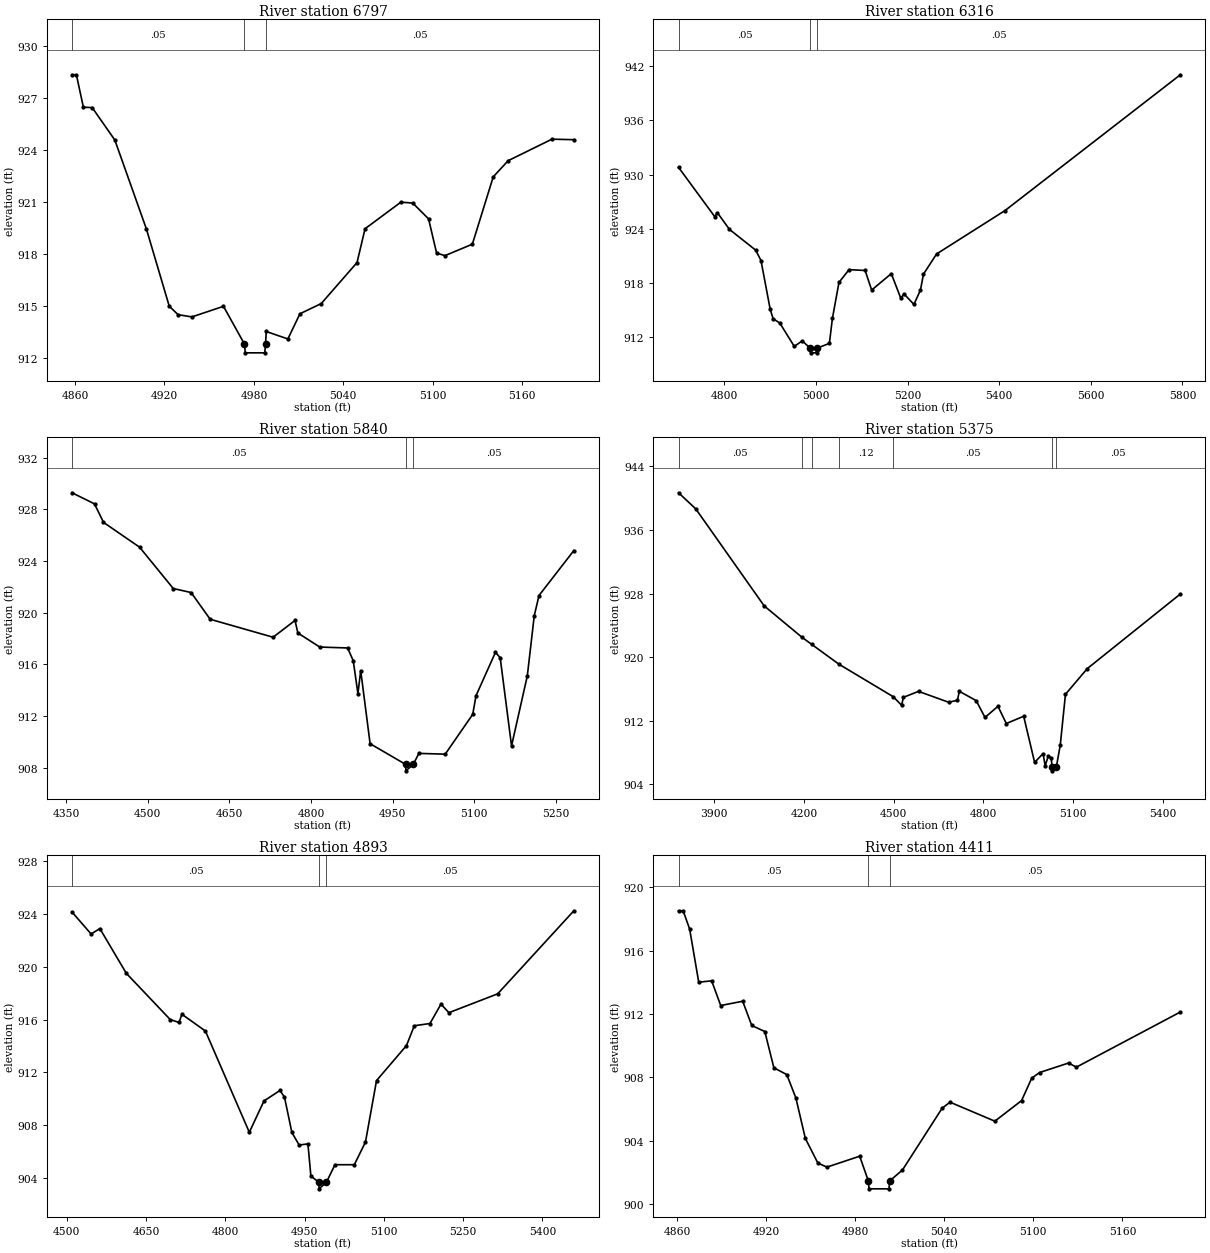
Type RM Length L Ch R = 1 ,6797    ,481,481,481
BEGIN DESCRIPTION:
SANDY CREEK 10.0
END DESCRIPTION:
XS GIS Cut Line= 3
      2874755.66     10233103.15       2874679.5       10233223.
      2874605.67     10233403.16
#Sta/Elev= 30
    4858  928.33  4860.9  928.33  4865.6  926.46  4871.5  926.44  4886.7  924.57
  4907.9  919.44  4923.2     915  4929.1  914.51  4938.4  914.38  4959.6  914.99
  4973.7  912.81  4974.2  912.31  4987.3  912.31  4987.8  912.81  4988.3  913.54
  5002.8  913.11  5010.9  914.56  5025.2  915.15  5049.2  917.51  5054.6  919.46
  5078.6  920.99  5086.6  920.94  5097.2  920.03  5102.6  918.06  5108.2  917.91
  5126.6  918.57  5140.6  922.45  5150.6  923.38    5180  924.62  5194.7  924.59
#Mann= 3 ,-1 , 0
    4858     .05       0  4973.7     .03       0  4987.8     .05       0
Bank Sta=4973.7,4987.8
XS Rating Curve= 0 ,0
Exp/Cntr=0.3,0.1

Type RM Length L Ch R = 1 ,6316    ,476,476,476
BEGIN DESCRIPTION:
SANDY CREEK 9.0
END DESCRIPTION:
XS GIS Cut Line= 3
      2874755.68     10232703.11      2874470.75       10232797.
      2873955.69     10233403.11
#Sta/Elev= 30
    4700   930.8  4779.4  925.31  4784.7  925.78  4811.2  923.92  4868.5  921.62
    4880  920.47    4900  915.09  4906.5  914.02  4921.1  913.54  4952.7  910.95
    4970  911.57  4987.7  910.74  4988.2  910.24  5001.3  910.24  5001.8  910.74
  5029.3  911.29  5035.9  914.05  5050.2  918.04  5072.2  919.46  5107.3  919.37
  5121.6   917.2  5164.5  919.02  5185.3  916.27  5191.9  916.78  5213.9  915.61
  5228.1   917.2  5234.7  918.96  5263.3   921.2  5412.7  926.01  5795.4  941.06
#Mann= 3 ,-1 , 0
    4700     .05       0  4987.7     .05       0  5001.8     .05       0
Bank Sta=4987.7,5001.8
XS Rating Curve= 0 ,0
Exp/Cntr=0.3,0.1

Type RM Length L Ch R = 1 ,5840    ,465,465,465
BEGIN DESCRIPTION:
SANDY CREEK 8.0
END DESCRIPTION:
XS GIS Cut Line= 3
      2874855.64      10232553.1       2874237.5       10232390.
      2874005.64     10232553.14
#Sta/Elev= 30
  4360.7  929.29    4402  928.43  4418.5     927  4484.8  925.08  4546.8  921.88
  4579.6  921.57  4614.7   919.5  4730.4  918.11  4770.7  919.41  4775.9  918.44
  4816.2  917.35  4867.4  917.28  4877.8  916.29  4886.4  913.74  4891.5  915.53
  4908.8  909.87  4974.1  908.27  4974.6  907.77  4988.3  908.27  4998.4  909.12
  5046.9  909.06  5097.5  912.14  5103.6  913.59  5139.3  916.94    5148  916.53
  5168.9   909.7  5197.9  915.12  5210.7  919.78  5219.4  921.34  5283.5  924.82
#Mann= 3 ,-1 , 0
  4360.7     .05       0  4974.1     .05       0  4988.3     .05       0
Bank Sta=4974.1,4988.3
XS Rating Curve= 0 ,0
Exp/Cntr=0.3,0.1

Type RM Length L Ch R = 1 ,5375    ,482,482,482
BEGIN DESCRIPTION:
SANDY CREEK 7.0
END DESCRIPTION:
XS GIS Cut Line= 3
      2875005.66     10231303.13        2874013.       10232011.
      2873555.64     10232053.12
#Sta/Elev= 30
  3780.8  940.68  3838.5  938.65  4067.2  926.45  4192.6  922.53  4226.7  921.59
  4317.7   919.1  4499.3  915.01  4526.9  913.94  4533.1  914.94  4583.5  915.69
  4684.3  914.32  4713.8  914.57  4719.9   915.7  4776.4  914.53  4805.9  912.41
  4849.3  913.81  4877.2  911.64  4935.3  912.56  4971.9  906.75    5000  907.86
  5007.3  906.33  5017.4  907.53  5027.4  907.31  5030.3  906.19  5030.8  905.69
  5044.6  906.19  5057.6  908.91  5075.1  915.32  5147.9  918.55  5459.3  927.94
#Mann= 7 ,-1 , 0
  3780.8     .05       0  4192.6     .12       0  4226.7     .05       0
  4317.7     .12       0  4499.3     .05       0  5030.3     .05       0
  5044.6     .05       0
Bank Sta=5030.3,5044.6
XS Rating Curve= 0 ,0
Exp/Cntr=0.3,0.1

Type RM Length L Ch R = 1 ,4893    ,482,482,482
BEGIN DESCRIPTION:
SANDY CREEK 6.0
END DESCRIPTION:
XS GIS Cut Line= 3
      2874155.66     10231103.15      2873931.75       10231539.
      2873555.72     10231803.09
#Sta/Elev= 30
    4510  924.15    4546  922.49  4562.6   922.9  4612.6  919.51  4695.7     916
  4712.3  915.78  4717.9   916.4  4762.3  915.13  4845.4  907.45  4873.2  909.83
  4903.4  910.62  4911.9  910.12  4925.9  907.44  4939.7  906.48  4956.3  906.57
  4961.9  904.13    4977  903.66  4977.5  903.16  4991.3  903.66  5007.4  904.99
  5044.1  904.99  5065.2  906.71  5086.1  911.37  5142.8  914.03  5157.6  915.53
  5187.2   915.7  5208.1  917.17    5223  916.52  5315.3  917.95  5459.5  924.25
#Mann= 3 ,-1 , 0
    4510     .05       0    4977     .03       0  4991.3     .05       0
Bank Sta=4977,4991.3
XS Rating Curve= 0 ,0
Exp/Cntr=0.3,0.1

Type RM Length L Ch R = 1 ,4411    ,451,451,451
BEGIN DESCRIPTION:
SANDY CREEK 5.0
END DESCRIPTION:
XS GIS Cut Line= 3
      2873655.71     10231153.07      2873576.25       10231267.
       2873505.7     10231453.07
#Sta/Elev= 30
  4861.1  918.52  4864.2  918.52  4868.6  917.36  4874.7  914.01  4883.4   914.1
  4889.5  912.54  4904.3  912.81  4910.4  911.28  4919.2   910.9  4925.3  908.61
    4934  908.18  4940.1  906.71  4946.5  904.15  4954.9   902.6    4961  902.34
  4983.1  903.03  4988.9  901.47  4989.4  900.97  5002.8  900.97  5003.3  901.47
  5011.9  902.16  5038.6  906.06  5043.9  906.44  5074.1  905.24  5092.1  906.54
  5098.9  907.95  5104.2  908.31  5123.7  908.91    5129  908.65    5199  912.13
#Mann= 3 ,-1 , 0
  4861.1     .05       0  4988.9     .03       0  5003.3     .05       0
Bank Sta=4988.9,5003.3
XS Rating Curve= 0 ,0
Exp/Cntr=0.3,0.1

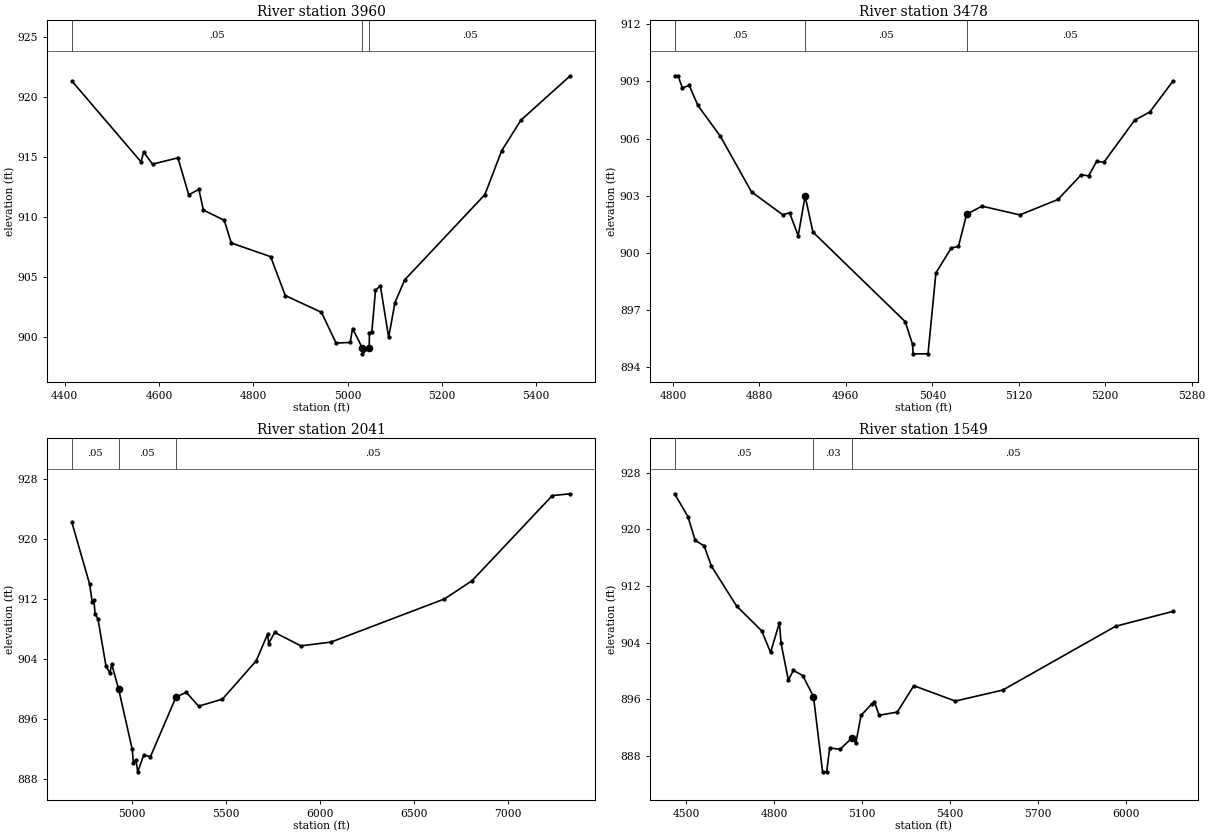
Type RM Length L Ch R = 1 ,3960    ,482,482,482
BEGIN DESCRIPTION:
SANDY CREEK 4.0
END DESCRIPTION:
XS GIS Cut Line= 3
      2873955.68     10231103.11        2873413.       10230886.
      2872955.66     10231003.12
#Sta/Elev= 30
  4415.5   921.3  4562.2  914.56  4567.6  915.39  4586.5  914.37  4640.3   914.9
  4663.2  911.82  4684.8  912.27  4694.2  910.55  4738.6  909.69  4753.4   907.8
  4836.9  906.66  4867.9  903.42  4944.6  902.02  4975.6  899.46  5005.5  899.51
  5010.6  900.67  5031.1  899.06  5031.6  898.56  5045.9  899.06  5046.3   900.3
  5051.4  900.39  5059.2  903.85  5069.5  904.24  5087.1  899.94  5100.5  902.83
  5121.1  904.73  5291.1  911.83  5326.7  915.49  5367.5  918.04  5472.1  921.74
#Mann= 3 ,-1 , 0
  4415.5     .05       0  5031.1     .03       0  5045.9     .05       0
Bank Sta=5031.1,5045.9
XS Rating Curve= 0 ,0
Exp/Cntr=0.3,0.1

Type RM Length L Ch R = 1 ,3478    ,1437,1437,1437
BEGIN DESCRIPTION:
SANDY CREEK 3.0
END DESCRIPTION:
XS GIS Cut Line= 3
      2873805.66     10230653.08      2873681.75       10230498.
      2873505.71     10230303.14
#Sta/Elev= 30
  4801.5   909.3  4804.7   909.3  4808.7  908.67  4815.1  908.79  4823.1  907.74
  4843.9  906.12  4872.7   903.2  4901.5     902  4907.9   902.1  4915.9   900.9
  4922.3  902.98  4929.5  901.09  5014.9  896.38  5021.7  895.19  5022.2  894.69
    5036  894.69  5043.3  898.94  5057.5  900.25  5064.2  900.34  5071.7  902.02
  5085.9  902.45    5121  901.99  5156.2   902.8  5177.8   904.1  5184.6  904.04
    5192   904.8  5198.8  904.76  5227.1  906.96  5241.3   907.4  5262.6  909.02
#Mann= 3 , 0 , 0
  4801.5     .05       0  4922.3     .05       0  5071.7     .05       0
Bank Sta=4922.3,5071.7
XS Rating Curve= 0 ,0
Exp/Cntr=0.3,0.1

Type RM Length L Ch R = 1 ,2041    ,492,492,492
BEGIN DESCRIPTION:
SANDY CREEK 2.0
END DESCRIPTION:
XS GIS Cut Line= 3
      2874955.73     10229753.14       2874687.5       10229584.
      2872505.69     10230403.11
#Sta/Elev= 30
  4682.9  922.26  4777.5     914  4790.7  911.62    4800  911.91  4805.9  910.08
  4821.2  909.41  4863.6  903.17  4884.8  902.14  4894.2  903.38  4930.7  900.07
  5003.6  891.98  5009.5  890.16  5023.3  890.58  5032.8  888.99  5064.6  891.24
  5100.2  891.01  5235.5  898.95  5290.3   899.6  5356.4  897.75  5482.6  898.69
  5662.5  903.81    5723  907.39  5728.3   906.1  5760.3  907.59  5899.2   905.8
  6059.2   906.3  6662.4  912.06  6808.3  914.48  7235.3  925.85  7330.5  926.09
#Mann= 3 , 0 , 0
  4682.9     .05       0  4930.7     .05       0  5235.5     .05       0
Bank Sta=4930.7,5235.5
XS Rating Curve= 0 ,0
Exp/Cntr=0.3,0.1

Type RM Length L Ch R = 1 ,1549    ,0,0,0
BEGIN DESCRIPTION:
SANDY CREEK 1.0
END DESCRIPTION:
XS GIS Cut Line= 3
      2875255.65      10229303.1        2874750.       10229115.
      2873655.69     10229503.11
#Sta/Elev= 30
  4460.5     925    4506  921.79    4531  918.41  4561.3  917.65  4586.3  914.78
    4672  909.17  4757.7  905.66  4788.1  902.61  4818.4  906.81  4823.8  903.91
  4848.8   898.7  4865.9  900.07  4897.9  899.34  4934.5  896.38  4965.6  885.75
  4979.6  885.75  4989.8  889.11  5025.8  888.94    5066  890.55  5078.9  889.79
  5096.9  893.72  5133.1  895.32  5142.5  895.62  5158.7  893.74  5220.4  894.18
  5276.9  897.91  5418.4  895.74  5580.3  897.29  5965.7   906.3  6161.1   908.4
#Mann= 3 , 0 , 0
  4460.5     .05       0  4934.5     .03       0    5066     .05       0
Bank Sta=4934.5,5066
XS Rating Curve= 0 ,0
Exp/Cntr=0.3,0.1

Chan Stop Cuts=-1
Use User Specified Reach Order=0
Composite Channel Slope=5