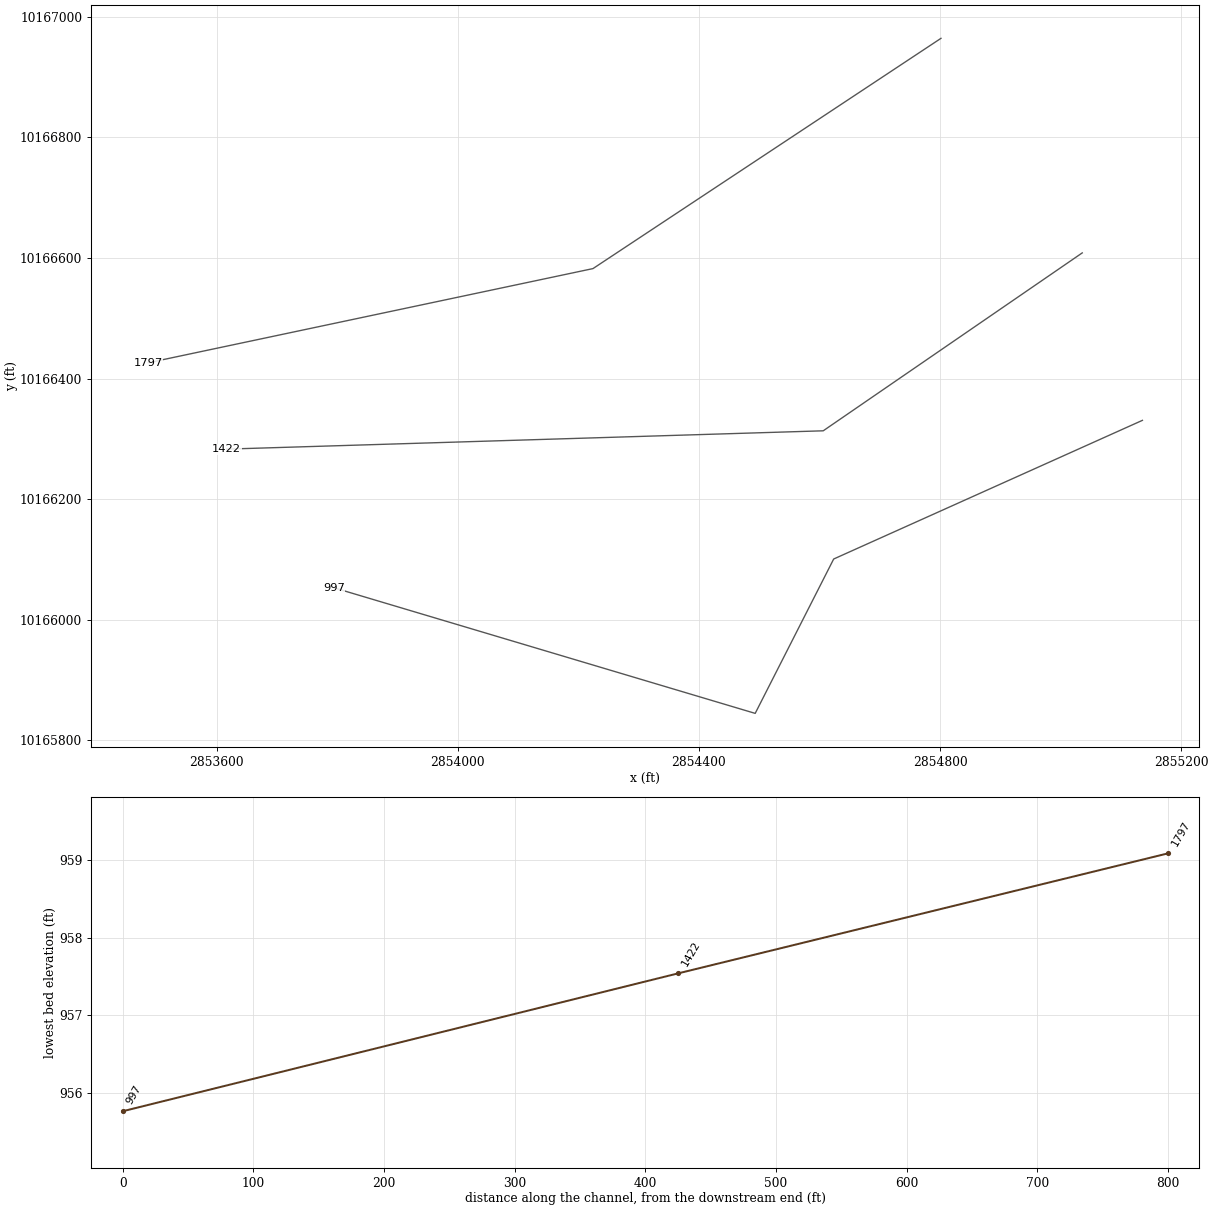
HEC-RAS study BARNETT BRANCH.prj: BARNETT BRANCH Base Level Engineering

--- BARNETT BRANCH.g01 (geometry) --- (continued)

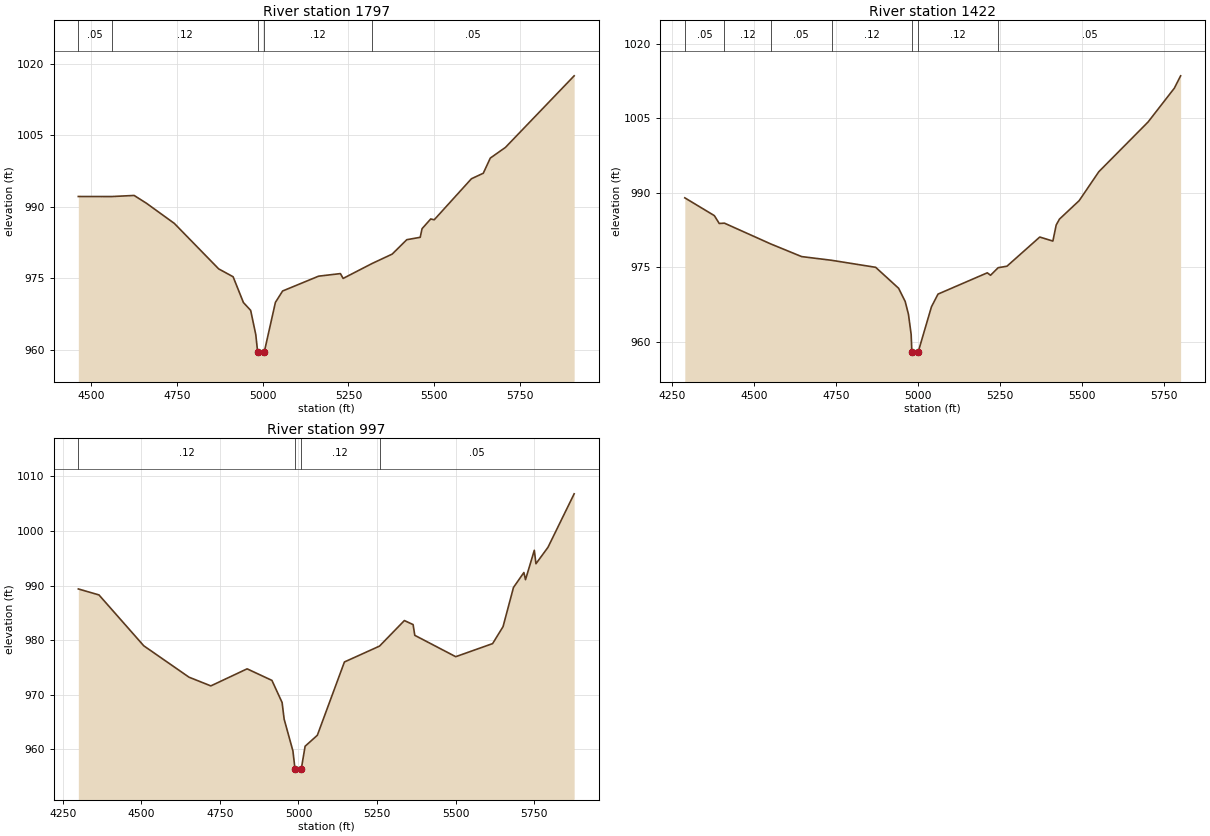
Type RM Length L Ch R = 1 ,1797    ,375,375,375
BEGIN DESCRIPTION:
BARNETT BRANCH 4.0
END DESCRIPTION:
XS GIS Cut Line= 3
      2854801.48     10166964.45      2854224.19     10166582.48
      2853486.37     10166426.24
#Sta/Elev= 30
    4462  992.15  4559.4  992.14  4624.8  992.37  4660.8  990.73    4742  986.51
  4871.4  976.97  4913.5  975.32  4943.6  969.91  4964.7  968.27  4979.7  963.17
    4985  959.59  4985.5  959.09  5004.6  959.59  5036.9  969.94  5057.9  972.33
  5162.9  975.44  5226.5  975.98  5234.5  974.97    5319   978.1  5377.6  980.07
  5420.1  983.09  5459.3  983.59  5464.7   985.4    5490  987.44  5500.2  987.27
  5608.7  995.87  5643.3  997.03  5663.8 1000.21    5708 1002.45  5908.4 1017.46
#Mann= 5 ,-1 , 0
    4462     .05       0  4559.4     .12       0    4985     .07       0
  5004.6     .12       0    5319     .05       0
Bank Sta=4985,5004.6
XS Rating Curve= 0 ,0
Exp/Cntr=0.3,0.1

Type RM Length L Ch R = 1 ,1422    ,425,425,425
BEGIN DESCRIPTION:
BARNETT BRANCH 3.0
END DESCRIPTION:
XS GIS Cut Line= 3
      2855035.85     10166608.54      2854606.14     10166313.39
      2853616.52       10166283.
#Sta/Elev= 30
  4289.4  988.99  4379.5  985.41  4394.4  983.83  4410.3  983.89  4551.5  979.71
  4645.4  977.17    4737  976.42  4871.2  975.01  4941.2  970.79  4961.2  968.14
  4971.2  965.55  4979.4   961.5  4981.5  958.04    4982  957.54  5001.1  958.04
  5041.3  967.07  5061.3  969.62  5211.4   973.9  5221.4  973.41  5244.6  974.93
  5271.4  975.23  5371.4   981.1  5411.4  980.29  5421.5  983.52  5431.5  984.71
  5491.5  988.42  5551.5  994.25  5701.6 1004.25  5781.6 1011.05  5800.8 1013.54
#Mann= 7 ,-1 , 0
  4289.4     .05       0  4410.3     .12       0  4551.5     .05       0
    4737     .12       0  4981.5     .07       0  5001.1     .12       0
  5244.6     .05       0
Bank Sta=4981.5,5001.1
XS Rating Curve= 0 ,0
Exp/Cntr=0.3,0.1

Type RM Length L Ch R = 1 ,997     ,0,0,0
BEGIN DESCRIPTION:
BARNETT BRANCH 2.0
END DESCRIPTION:
XS GIS Cut Line= 4
      2855135.65     10166330.74       2854623.5     10166100.71
      2854493.29     10165844.64       2853794.5     10166052.97
#Sta/Elev= 30
  4299.4  989.37  4365.1  988.27  4507.6  978.94  4651.6  973.18  4721.1  971.58
  4836.5  974.71  4915.5  972.59  4947.9  968.53  4954.4  965.47  4982.3  959.65
  4989.1  956.26  4989.6  955.76  5008.7  956.26  5021.1  960.51    5060  962.52
  5146.2  975.97  5257.9  978.88    5337  983.57  5364.8  982.83  5370.1  980.86
  5500.4  976.94  5617.8  979.34    5651  982.45  5684.2  989.64  5717.3  992.38
  5722.5  991.07  5750.5  996.46  5755.7  993.99    5794  997.01  5877.3 1006.82
#Mann= 4 ,-1 , 0
  4299.4     .12       0  4989.1     .07       0  5008.7     .12       0
  5257.9     .05       0
Bank Sta=4989.1,5008.7
XS Rating Curve= 0 ,0
Exp/Cntr=0.3,0.1

Chan Stop Cuts=-1
Use User Specified Reach Order=0
Composite Channel Slope=5