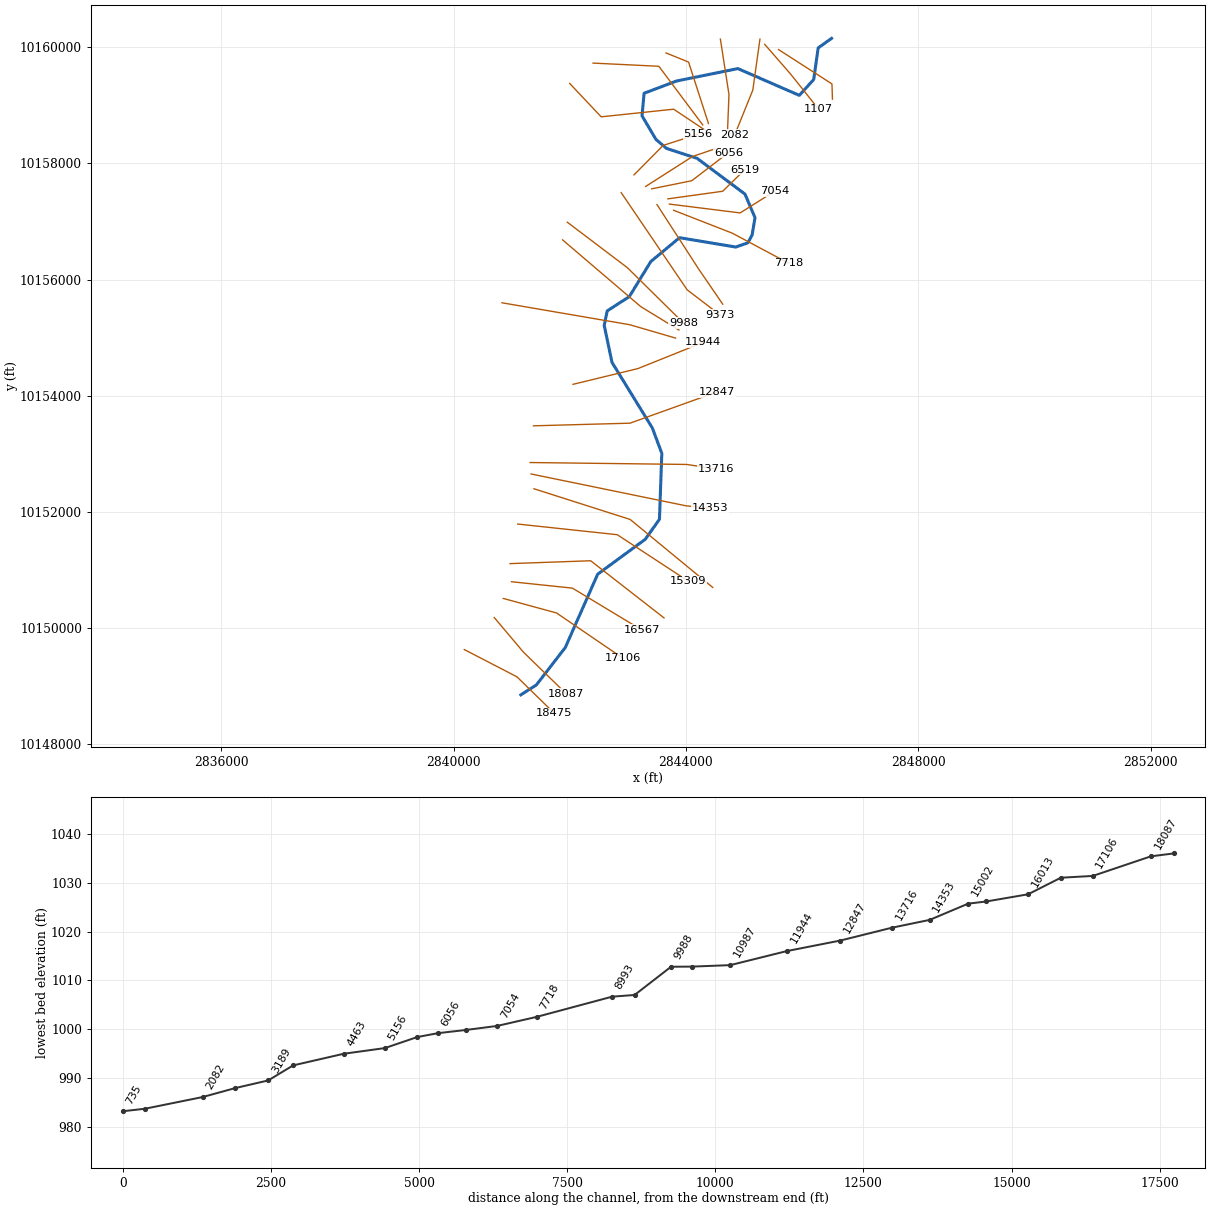
--- COAL CREEK.prj (project) ---

Proj Title=COAL CREEK Base Level Engineering
Current Plan=p01
Default Exp/Contr=0.3,0.1
English Units
Geom File=g01
Flow File=f01
Plan File=p01
Y Axis Title=Elevation
X Axis Title(PF)=Main Channel Distance
X Axis Title(XS)=Station
BEGIN DESCRIPTION:
COAL CREEK
END DESCRIPTION:
DSS Export Rating Curves= 0
DSS Export Rating Curve Sorted= 0
DSS Export Volume Flow Curves= 0
DXF OffsetX= 0
DXF OffsetY= 0
DXF ScaleX= 1
DXF ScaleY= 10

--- COAL CREEK.p01 (plan) ---

Plan Title=Multiple Run
Short Identifier=Multiple
Geom File=g01
Flow File=f01
Subcritical Flow
K Sum by GR= 0
Std Step Tol= 0.01
Critical Tol= 0.01
Num of Std Step Trials= 20
Max Error Tol= 0.3
Flow Tol Ratio= 0.001
Split Flow NTrial= 30
Split Flow Tol= 0.02
Split Flow Ratio= 0.02
Log Output Level= 0
Friction Slope Method= 1
Unsteady Friction Slope Method= 2
Unsteady Bridges Friction Slope Method= 1
Parabolic Critical Depth
Global Vel Dist=  1 , 1 , 1
Global Log Level= 0
CheckData=True
Encroach Param= -1, 0, 0, 0
BEGIN DESCRIPTION:
Multiple Run
END DESCRIPTION:

--- COAL CREEK.f01 (steady flow) ---

Flow Title=Multiple
Number of Profiles=7
Profile Names=10-year,25-year,50-year,1pct_min,100-year,1pct_plu,500-year
River Rch & RM= COAL CREEK,Reach-1,18475
   18066   33958   53989   39296   76861  150338  100366
River Rch & RM= COAL CREEK,Reach-1,15309
   17847   33536   53284   38847   75853  148113   99037
River Rch & RM= COAL CREEK,Reach-1,13716
   18286   34341   54460   39656   77482  151390  101089
River Rch & RM= COAL CREEK,Reach-1,12847
   17784   33392   52929   38653   75309  146727   98254
River Rch & RM= COAL CREEK,Reach-1,10987
   17361   32588   51611   37802   73433  142647   95797
River Rch & RM= COAL CREEK,Reach-1,7718
   16247   30513   48367   35634   68868  133097   89909
River Rch & RM= COAL CREEK,Reach-1,3609
   16458   30864   48706   35920   69274  133598   90305
Boundary for River Rch & Prof#=COAL CREEK,Reach-1,1
Up Type=0
Dn Type=3
Dn Slope=0.005
Boundary for River Rch & Prof#=COAL CREEK,Reach-1,2
Up Type=0
Dn Type=3
Dn Slope=0.005
Boundary for River Rch & Prof#=COAL CREEK,Reach-1,3
Up Type=0
Dn Type=3
Dn Slope=0.005
Boundary for River Rch & Prof#=COAL CREEK,Reach-1,4
Up Type=0
Dn Type=3
Dn Slope=0.005
Boundary for River Rch & Prof#=COAL CREEK,Reach-1,5
Up Type=0
Dn Type=3
Dn Slope=0.005
Boundary for River Rch & Prof#=COAL CREEK,Reach-1,6
Up Type=0
Dn Type=3
Dn Slope=0.005
Boundary for River Rch & Prof#=COAL CREEK,Reach-1,7
Up Type=0
Dn Type=3
Dn Slope=0.005

--- COAL CREEK.g01 (geometry) ---

Geom Title=Existing Conditions
Program Version=4.10

River Reach=COAL CREEK      ,Reach-1
Reach XY= 30
      2841157.12     10148849.31      2841424.04     10149019.66
      2841922.09      10149664.2      2842480.25       10150927.
       2843298.5       10151527.      2843543.75       10151872.
        2843584.       10153008.       2843420.5       10153445.
      2842726.25       10154574.      2842592.25       10155211.
      2842644.25       10155461.       2843024.5       10155706.
      2843394.25       10156310.        2843889.       10156721.
      2844857.75       10156560.      2845066.25       10156633.
        2845139.       10156768.      2845189.25       10157066.
      2845016.25       10157472.      2844192.75       10158087.
      2843665.25       10158258.      2843482.75       10158414.
       2843243.5       10158819.      2843278.75       10159208.
        2843837.       10159419.      2844894.25       10159633.
       2845951.5       10159172.        2846200.       10159445.
       2846276.5       10159989.      2846507.75       10160154.

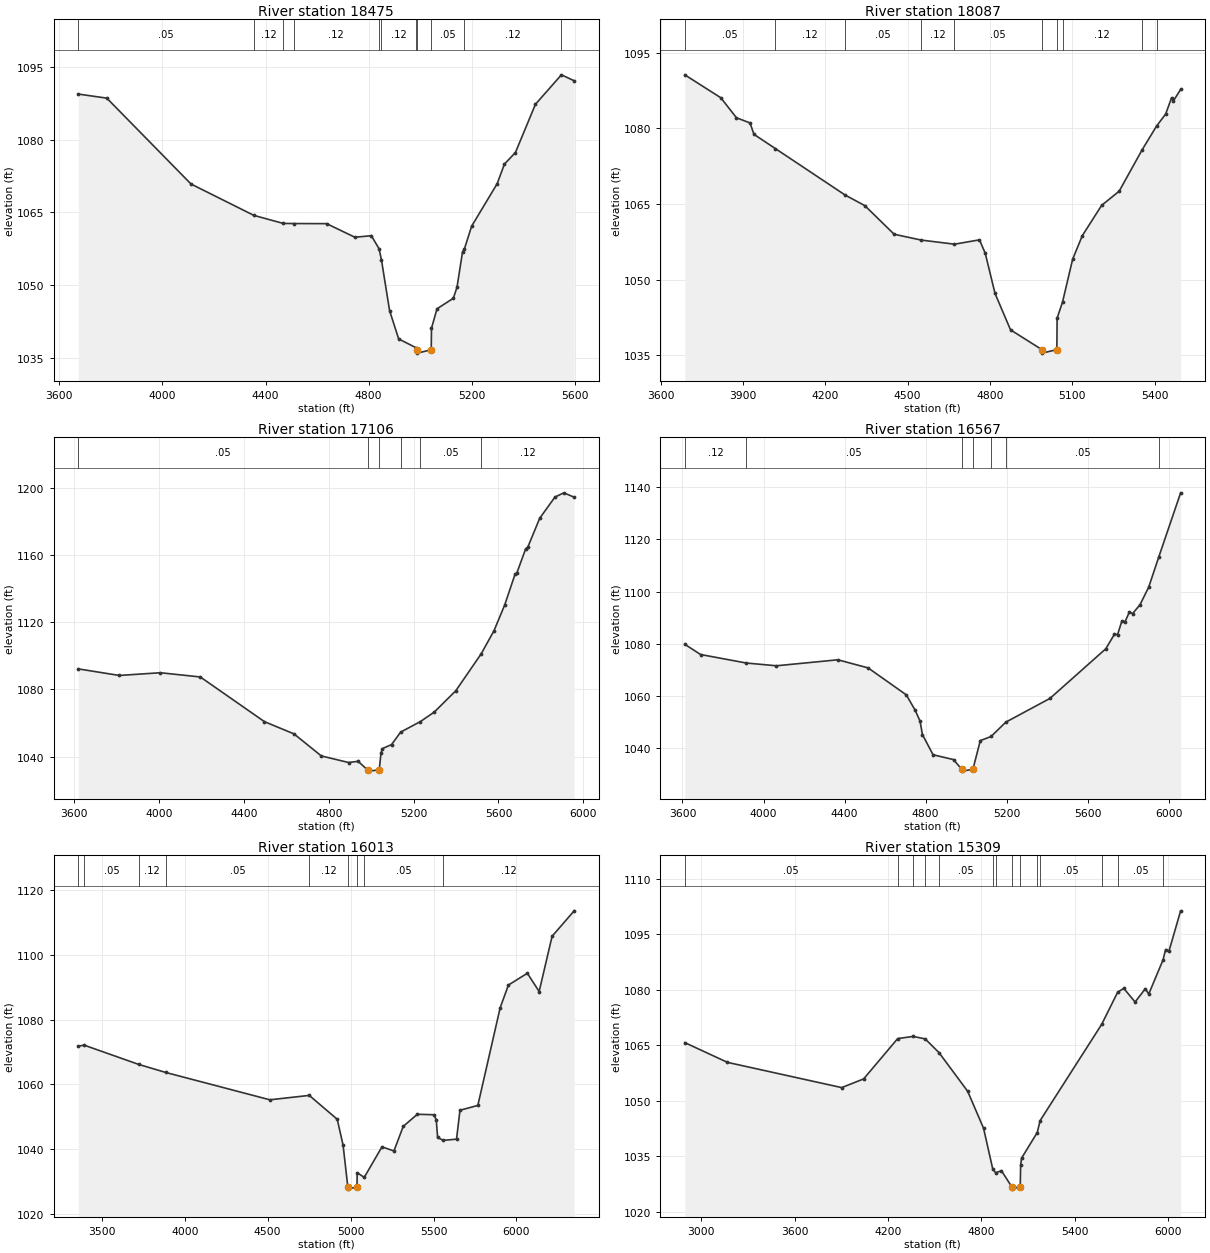
Type RM Length L Ch R = 1 ,18475   ,388,388,388
BEGIN DESCRIPTION:
Mapping XS a8bbd2f7
END DESCRIPTION:
XS GIS Cut Line= 3
      2840182.45     10149628.75      2841088.72     10149159.98
      2841734.56     10148529.77
#Sta/Elev= 30
  3674.2 1089.37  3784.6 1088.53  4111.1 1070.86  4354.9  1064.4  4468.6 1062.75
  4508.9 1062.72  4636.9  1062.7  4746.7  1059.9  4810.4 1060.22  4840.3 1057.54
  4849.8  1055.2  4881.1 1044.81  4916.4 1038.97  4984.3 1037.15  4988.1 1036.75
  4989.3 1036.05  5042.7 1036.75  5043.7 1041.16    5065 1045.17  5128.6 1047.35
  5142.7 1049.64    5164 1056.87  5171.3  1057.5  5199.3 1062.17  5298.3 1070.92
  5326.6 1074.97  5369.1 1077.33  5446.8 1087.27  5547.5 1093.33  5596.9 1092.11
#Mann= 11 ,-1 , 0
  3674.2     .05       0  4354.9     .12       0  4468.6     .05       0
  4508.9     .12       0  4840.3     .05       0  4849.8     .12       0
  4984.3     .05       0  4988.1     .03       0  5042.7     .05       0
  5171.3     .12       0  5547.5     .05       0
Bank Sta=4988.1,5042.7
XS Rating Curve= 0 ,0
Exp/Cntr=0.3,0.1

Type RM Length L Ch R = 1 ,18087   ,981,981,981
BEGIN DESCRIPTION:
Mapping XS 4edef2bb
END DESCRIPTION:
XS GIS Cut Line= 3
      2840698.12     10150180.79       2841203.3     10149581.86
       2841937.7      10148868.3
#Sta/Elev= 30
  3687.5 1090.58  3818.7 1086.04  3875.9 1082.07  3925.3 1081.05  3939.6 1078.79
  4017.7 1075.97  4271.6 1066.78    4344 1064.66  4450.6    1059  4548.8 1057.85
  4670.6 1057.03  4761.8 1057.89  4782.9 1055.21  4818.4 1047.27    4875 1040.06
  4989.1 1036.15  4990.3 1035.45  5043.8 1036.15  5044.7 1042.36  5064.6 1045.59
  5101.3 1054.04  5136.6 1058.72  5207.3 1064.74  5270.9 1067.52  5354.4  1075.7
  5407.2 1080.42  5440.6 1082.83  5461.9 1086.03  5468.9 1085.44    5495 1087.69
#Mann= 10 ,-1 , 0
  3687.5     .05       0  4017.7     .12       0  4271.6     .05       0
  4548.8     .12       0  4670.6     .05       0  4989.1     .05       0
  5043.8     .05       0  5064.6     .12       0  5354.4     .05       0
  5407.2     .12       0
Bank Sta=4989.1,5043.8
XS Rating Curve= 0 ,0
Exp/Cntr=0.3,0.1

Type RM Length L Ch R = 1 ,17106   ,539,539,539
BEGIN DESCRIPTION:
Mapping XS 82e7fe2c
END DESCRIPTION:
XS GIS Cut Line= 3
      2840854.39     10150508.93      2841771.01     10150258.94
      2842916.57     10149477.88
#Sta/Elev= 30
    3620 1092.22  3813.1 1088.32  4006.6 1089.94  4194.9 1087.42  4497.2 1060.84
  4636.3 1053.58  4765.1 1040.46  4893.8 1036.55  4938.6 1037.28  4982.8 1032.13
    4984 1031.43    5038 1032.13  5046.3    1042  5052.4 1044.79  5096.2 1047.23
  5138.9 1054.63  5232.3 1060.92  5297.6 1066.58  5398.8 1079.23  5518.4 1101.17
  5578.8 1114.92  5628.7 1130.05  5677.7 1148.38  5686.6  1149.3  5728.5 1163.75
  5737.4 1164.41  5794.3  1181.8  5866.1  1194.4    5908 1196.92  5956.6 1194.33
#Mann= 6 ,-1 , 0
    3620     .05       0  4982.8     .03       0    5038     .05       0
  5138.9     .12       0  5232.3     .05       0  5518.4     .12       0
Bank Sta=4982.8,5038
XS Rating Curve= 0 ,0
Exp/Cntr=0.3,0.1

Type RM Length L Ch R = 1 ,16567   ,554,554,554
BEGIN DESCRIPTION:
COAL CREEK 28.0
END DESCRIPTION:
XS GIS Cut Line= 3
      2840996.12     10150796.54      2842044.49     10150686.56
      2843237.05     10149967.67
#Sta/Elev= 30
  3611.5 1079.76  3689.4 1075.84  3914.9 1072.57  4063.5 1071.51  4366.7 1073.81
    4516  1070.7  4704.6 1060.34  4748.8 1054.35  4772.1 1050.28  4784.2 1045.07
  4836.6 1037.34  4937.6 1035.49  4977.9 1031.76  4979.1 1031.06  5033.1 1031.76
  5069.6 1042.78  5122.8 1044.36  5195.4 1049.86  5413.3 1058.98    5689 1078.05
  5731.7 1083.65  5747.2 1083.51  5768.6 1088.81  5784.1 1088.45  5805.5 1092.21
    5821 1091.53  5857.9    1095  5900.6 1101.71  5950.6 1113.37  6058.1 1137.92
#Mann= 7 ,-1 , 0
  3611.5     .12       0  3914.9     .05       0  4977.9     .05       0
  5033.1     .05       0  5122.8     .12       0  5195.4     .05       0
  5950.6     .12       0
Bank Sta=4977.9,5033.1
XS Rating Curve= 0 ,0
Exp/Cntr=0.3,0.1

Type RM Length L Ch R = 1 ,16013   ,704,704,704
BEGIN DESCRIPTION:
COAL CREEK 27.0
END DESCRIPTION:
XS GIS Cut Line= 3
      2840971.52     10151108.56      2842359.21     10151157.83
      2843622.18      10150173.7
#Sta/Elev= 30
  3358.3 1071.83  3393.4 1072.15  3721.3 1066.21  3885.9  1063.7  4513.2 1055.26
  4750.8 1056.62  4919.5 1049.24  4954.7 1041.25  4983.2 1028.36  4984.4 1027.66
  5038.4 1028.36  5039.8 1032.74  5082.2 1031.29  5189.1 1040.72  5261.4 1039.46
  5317.5 1047.06  5402.6 1050.79    5503 1050.64  5516.6 1049.02  5524.7 1043.62
  5558.8 1042.72  5638.7  1043.1  5659.5 1052.03  5767.2 1053.52    5902 1083.73
  5951.7 1090.72  6065.7 1094.36  6136.9 1088.72    6215 1105.79    6348 1113.65
#Mann= 9 ,-1 , 0
  3358.3     .12       0  3393.4     .05       0  3721.3     .12       0
  3885.9     .05       0  4750.8     .12       0  4983.2     .07       0
  5038.4     .12       0  5082.2     .05       0  5558.8     .12       0
Bank Sta=4983.2,5038.4
XS Rating Curve= 0 ,0
Exp/Cntr=0.3,0.1

Type RM Length L Ch R = 1 ,15309   ,307,307,307
BEGIN DESCRIPTION:
COAL CREEK 26.0
END DESCRIPTION:
XS GIS Cut Line= 3
      2841102.94     10151790.08      2842816.43     10151606.51
      2844041.63     10150805.32
#Sta/Elev= 30
  2893.5 1065.73  3167.8  1060.4    3902 1053.59  4043.2 1055.94    4262 1066.82
  4361.7  1067.4  4438.9 1066.73  4528.1    1063  4711.5 1052.62    4814 1042.62
  4873.6 1031.51  4893.1 1030.58  4928.5 1031.18  4994.3 1026.89  4995.6 1026.19
  5049.9 1026.89  5052.2  1032.6  5058.2 1034.55  5158.9 1041.46  5177.7 1044.69
  5573.2 1070.66  5676.4 1079.37  5715.6 1080.36    5788 1076.69  5854.4  1080.3
  5875.5 1078.81  5967.9 1088.09  5984.1 1090.86  6005.2 1090.34  6080.7  1101.3
#Mann= 14 ,-1 , 0
  2893.5     .05       0    4262     .12       0  4361.7     .05       0
  4438.9     .12       0  4528.1     .05       0  4873.6     .12       0
  4893.1     .05       0  4994.3     .05       0  5049.9     .05       0
  5158.9     .12       0  5177.7     .05       0  5573.2     .12       0
  5676.4     .05       0  5967.9     .12       0
Bank Sta=4994.3,5049.9
XS Rating Curve= 0 ,0
Exp/Cntr=0.3,0.1

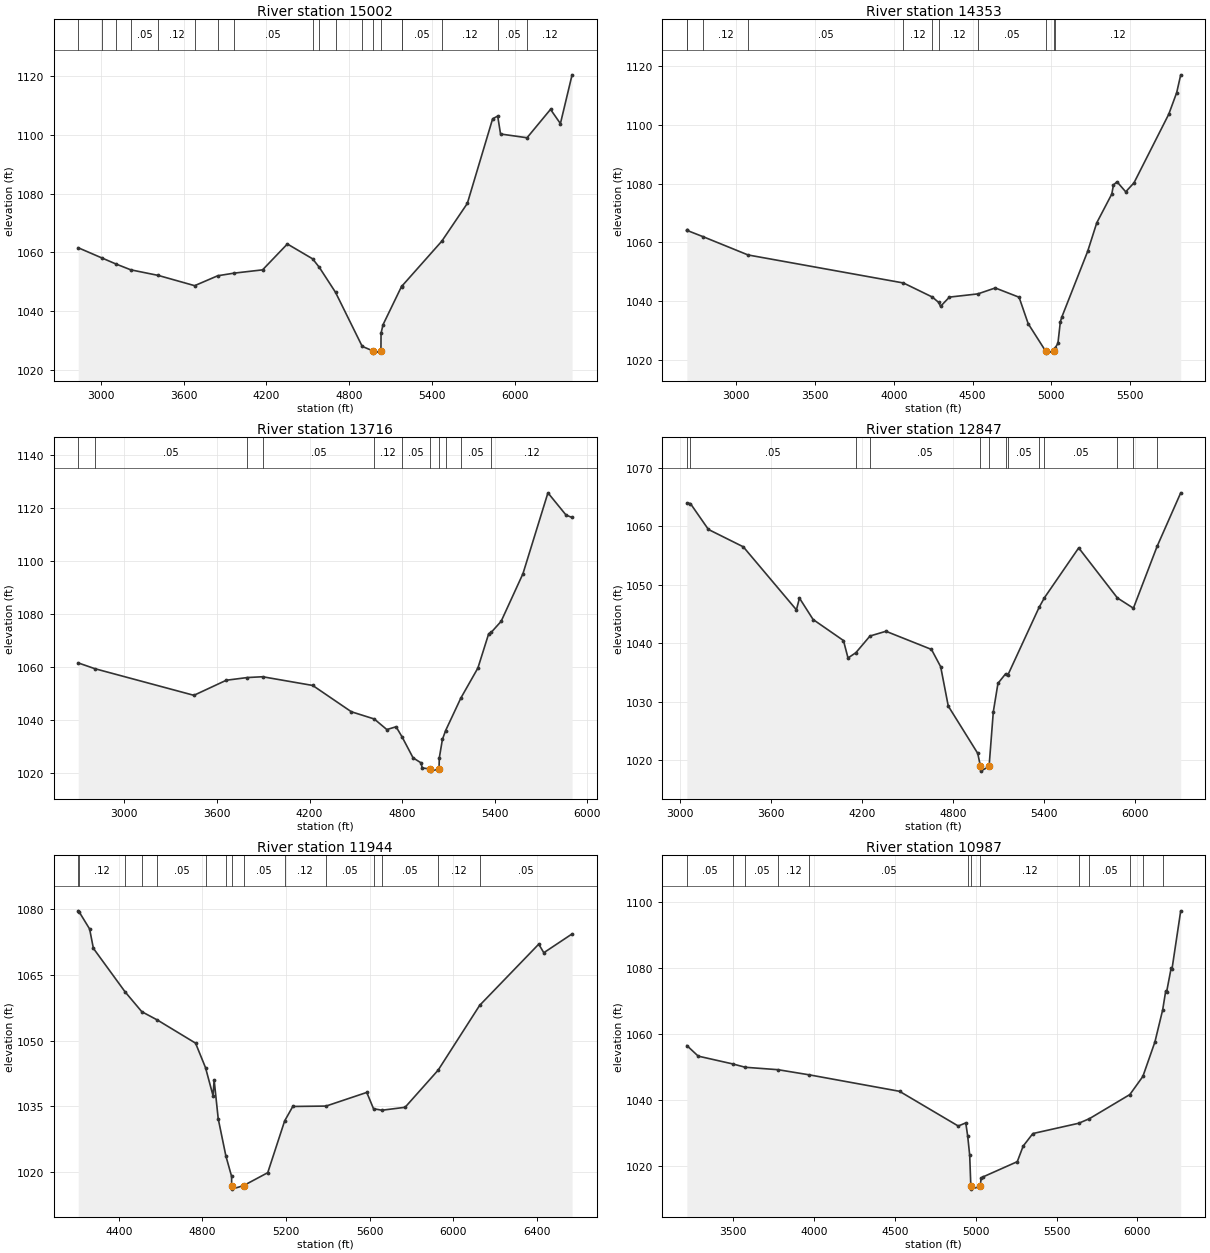
Type RM Length L Ch R = 1 ,15002   ,649,649,649
BEGIN DESCRIPTION:
COAL CREEK 25.0
END DESCRIPTION:
XS GIS Cut Line= 3
      2841382.05     10152397.72      2843038.78      10151869.3
      2844460.94     10150698.27
#Sta/Elev= 30
  2835.7 1061.59  3006.7 1058.13  3109.5 1056.06  3216.8 1054.08  3415.8 1052.18
  3679.9 1048.69  3847.2 1052.06  3965.1 1052.95  4172.5 1054.07  4352.2 1062.87
  4535.4 1057.82  4584.6 1054.88  4701.4 1046.43  4894.9 1028.05  4975.1 1026.44
  4976.4 1025.74  5030.7 1026.44  5031.6 1032.49    5046 1035.42  5179.9 1048.39
  5181.9 1048.49  5472.3 1063.84  5657.2 1076.67  5840.8 1105.47  5877.4 1106.38
  5898.2 1100.29  6090.2 1099.01  6260.5 1108.67  6332.2 1103.83  6416.9 1120.42
#Mann= 19 ,-1 , 0
  2835.7     .12       0  3006.7     .05       0  3109.5     .12       0
  3216.8     .05       0  3415.8     .12       0  3679.9     .05       0
  3847.2     .12       0  3965.1     .05       0  4535.4     .12       0
  4584.6     .05       0  4701.4     .12       0  4894.9     .05       0
  4975.1     .03       0  5030.7     .05       0  5179.9     .12       0
  5181.9     .05       0  5472.3     .12       0  5877.4     .05       0
  6090.2     .12       0
Bank Sta=4975.1,5030.7
XS Rating Curve= 0 ,0
Exp/Cntr=0.3,0.1

Type RM Length L Ch R = 1 ,14353   ,637,637,637
BEGIN DESCRIPTION:
COAL CREEK 24.0
END DESCRIPTION:
XS GIS Cut Line= 3
      2841332.84     10152652.25      2844005.68     10152103.11
      2844411.31     10152069.32
#Sta/Elev= 30
  2686.3 1064.09  2687.8 1064.09  2789.5 1061.96  3074.7 1055.76  4061.4 1046.24
  4245.4 1041.45  4284.7 1039.65    4297  1038.3  4353.2 1041.44  4533.7 1042.53
  4644.5 1044.55  4795.6  1041.4  4853.5 1032.41  4964.1 1023.11  4965.4 1022.41
  5019.8 1023.11  5026.4 1024.32  5042.3 1025.73  5057.7 1033.07  5067.9 1034.78
  5231.2    1057  5289.1 1066.71  5384.3 1076.45  5394.9 1079.54  5417.5 1080.62
  5472.7 1077.21  5525.4 1080.27  5746.1 1103.58  5796.3 1110.89    5822 1116.95
#Mann= 11 ,-1 , 0
  2686.3     .12       0  2687.8     .05       0  2789.5     .12       0
  3074.7     .05       0  4061.4     .12       0  4245.4     .05       0
  4284.7     .12       0  4533.7     .05       0  4964.1     .05       0
  5019.8     .05       0  5026.4     .12       0
Bank Sta=4964.1,5019.8
XS Rating Curve= 0 ,0
Exp/Cntr=0.3,0.1

Type RM Length L Ch R = 1 ,13716   ,869,869,869
BEGIN DESCRIPTION:
COAL CREEK 23.0
END DESCRIPTION:
XS GIS Cut Line= 3
      2841316.36     10152849.32      2844009.65     10152816.48
      2844510.53     10152742.58
#Sta/Elev= 30
  2701.3 1061.65  2809.6 1059.46  3450.7 1049.42  3660.7 1055.11  3797.3 1056.13
  3896.1 1056.43  4220.7 1053.14  4470.8 1043.22  4619.3 1040.49  4700.8  1036.5
  4760.8 1037.55  4799.6 1033.72  4870.8 1025.83  4920.8 1023.99  4930.8 1022.01
  4982.6 1021.61  4983.9 1020.81  5038.9 1021.61  5040.8 1025.81  5060.8 1032.75
  5081.4 1036.08  5180.2 1048.37  5290.8 1059.72  5360.8 1072.68  5377.7 1073.22
  5441.3 1077.34  5582.8 1095.33  5744.6 1125.84    5862 1117.45  5901.1 1116.53
#Mann= 11 ,-1 , 0
  2701.3     .12       0  2809.6     .05       0  3797.3     .12       0
  3896.1     .05       0  4619.3     .12       0  4799.6     .05       0
  4982.6     .05       0  5038.9     .05       0  5081.4     .12       0
  5180.2     .05       0  5377.7     .12       0
Bank Sta=4982.6,5038.9
XS Rating Curve= 0 ,0
Exp/Cntr=0.3,0.1

Type RM Length L Ch R = 1 ,12847   ,903,903,903
BEGIN DESCRIPTION:
COAL CREEK 21.0
END DESCRIPTION:
XS GIS Cut Line= 3
      2841373.87     10153481.58      2843036.17     10153527.04
      2844535.18     10154064.58
#Sta/Elev= 30
  3046.5 1063.97  3069.9 1063.87  3188.4 1059.45  3418.5 1056.48  3768.6 1045.72
  3788.6 1047.73  3878.6 1044.07  4078.7 1040.48  4108.7  1037.5  4160.4  1038.4
  4253.6 1041.25  4358.8 1042.06  4658.9 1038.96  4719.5 1036.01  4769.6 1029.29
  4963.9 1021.21    4982 1018.98  4983.3 1018.18  5038.6 1018.98  5066.5 1028.31
  5097.2 1033.17  5147.7  1034.8  5161.6 1034.54  5368.1 1046.13  5403.6 1047.79
  5629.4  1056.3  5884.5 1047.75    5990    1046  6145.9 1056.54  6301.9  1065.7
#Mann= 13 ,-1 , 0
  3046.5     .12       0  3069.9     .05       0  4160.4     .12       0
  4253.6     .05       0    4982     .05       0  5038.6     .05       0
  5147.7     .12       0  5161.6     .05       0  5368.1     .12       0
  5403.6     .05       0  5884.5     .12       0    5990     .05       0
  6145.9     .12       0
Bank Sta=4982,5038.6
XS Rating Curve= 0 ,0
Exp/Cntr=0.3,0.1

Type RM Length L Ch R = 1 ,11944   ,957,957,957
BEGIN DESCRIPTION:
COAL CREEK 20.0
END DESCRIPTION:
XS GIS Cut Line= 3
      2842055.36     10154195.94      2843172.11     10154466.91
      2844296.53     10154918.32
#Sta/Elev= 30
  4206.4 1079.65  4209.9 1079.48  4260.7 1075.51  4278.8 1071.08  4430.3 1061.13
  4510.2 1056.59  4585.3 1054.67  4767.2  1049.4  4814.8  1043.8  4850.8 1037.39
    4856 1040.99  4875.6 1032.11  4912.3 1023.58  4939.5 1018.94  4939.9 1016.82
  4941.1 1016.02  4996.6 1016.82  5112.3 1019.78  5193.2 1031.62    5232 1034.92
  5391.1 1035.01  5585.7 1038.13    5618  1034.4  5658.7 1034.06  5768.9 1034.73
    5927 1043.23  6125.4 1058.04  6407.8 1072.03    6432 1070.07  6567.2 1074.37
#Mann= 15 ,-1 , 0
  4206.4     .05       0  4209.9     .12       0  4430.3     .05       0
  4510.2     .12       0  4585.3     .05       0  4814.8     .12       0
  4912.3     .05       0  4939.9     .05       0  4996.6     .05       0
  5193.2     .12       0  5391.1     .05       0    5618     .12       0
  5658.7     .05       0    5927     .12       0  6125.4     .05       0
Bank Sta=4939.9,4996.6
XS Rating Curve= 0 ,0
Exp/Cntr=0.3,0.1

Type RM Length L Ch R = 1 ,10987   ,645,645,645
BEGIN DESCRIPTION:
COAL CREEK 19.0
END DESCRIPTION:
XS GIS Cut Line= 3
      2840831.89     10155600.06      2843032.52     10155222.34
      2843820.77     10154992.43
#Sta/Elev= 30
  3213.9 1056.53  3284.1 1053.33  3496.7 1050.98  3575.4 1049.96  3777.5 1049.23
  3971.3 1047.67  4528.8  1042.7  4891.9 1032.21  4938.6 1033.14  4950.6 1029.11
  4962.9 1023.33  4969.9 1013.93  4971.2 1013.13  5027.2 1013.93  5033.9 1016.46
  5044.1  1016.8  5257.1 1021.43  5293.5 1026.14  5353.5 1029.93    5637 1033.04
  5702.9 1034.42  5953.2 1041.72  6033.7 1047.19  6108.1  1057.6  6156.2 1067.31
    6175 1073.02  6180.2 1072.66  6208.5  1079.9  6213.7 1079.61  6267.8 1097.25
#Mann= 13 ,-1 , 0
  3213.9     .05       0  3496.7     .12       0  3575.4     .05       0
  3777.5     .12       0  3971.3     .05       0  4950.6     .12       0
  4969.9     .03       0  5027.2     .12       0    5637     .12       0
  5702.9     .05       0  5953.2     .12       0  6033.7     .05       0
  6156.2     .12       0
Bank Sta=4969.9,5027.2
XS Rating Curve= 0 ,0
Exp/Cntr=0.3,0.1

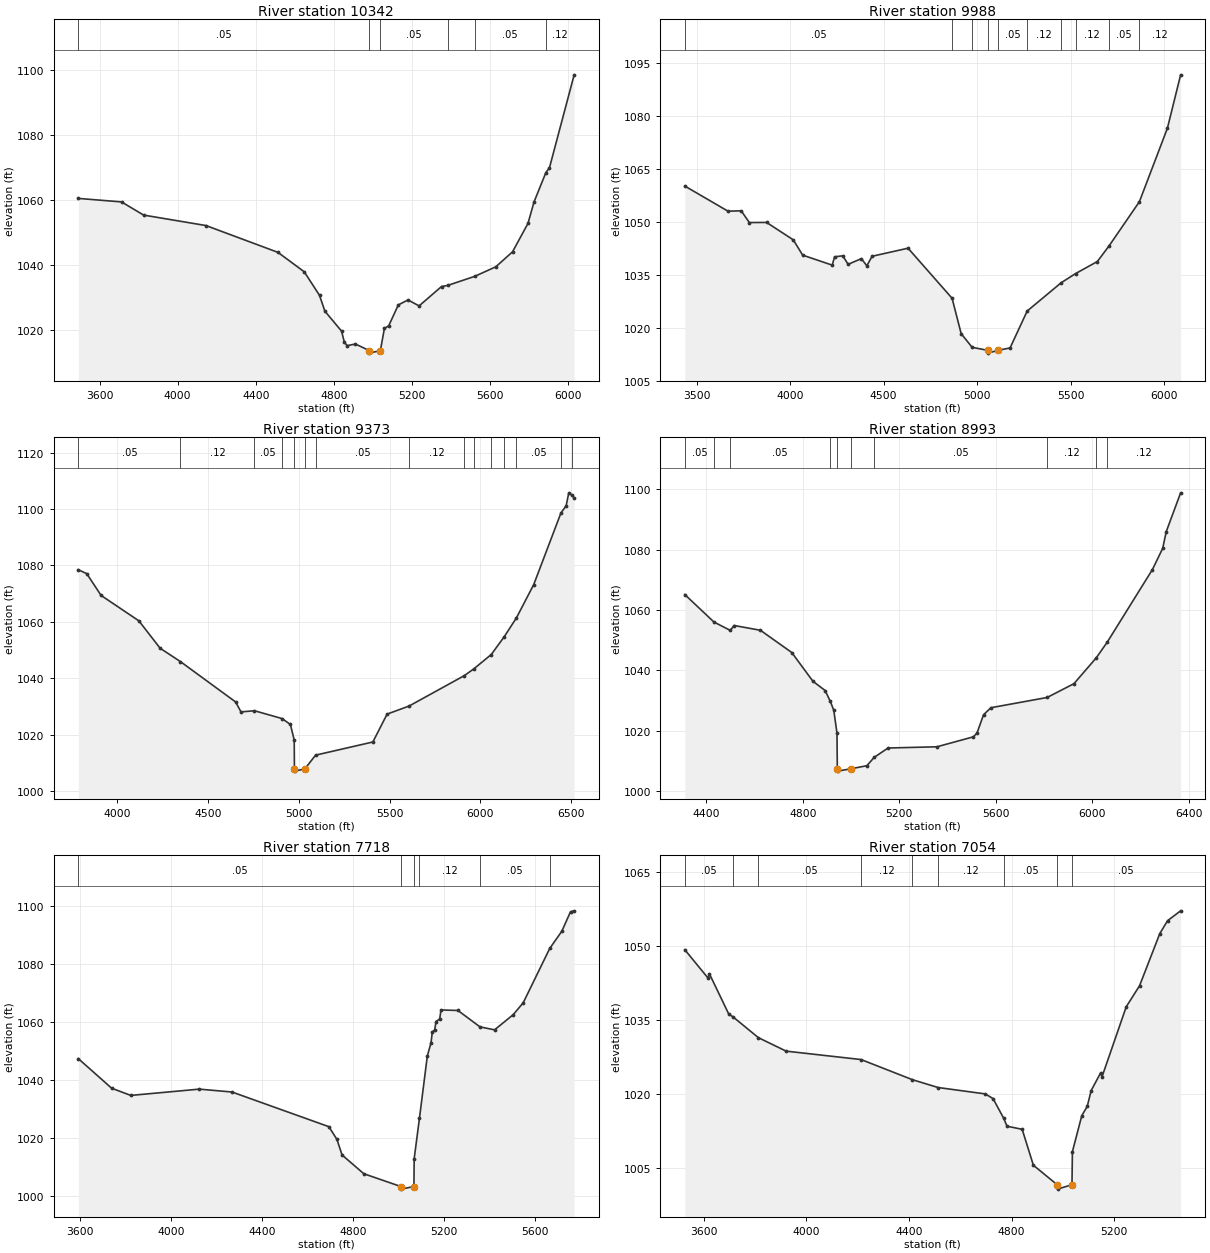
Type RM Length L Ch R = 1 ,10342   ,354,354,354
BEGIN DESCRIPTION:
COAL CREEK 18.0
END DESCRIPTION:
XS GIS Cut Line= 3
      2841874.73     10156683.94      2843221.38     10155534.36
      2843878.27     10155132.02
#Sta/Elev= 30
  3491.1 1060.44  3712.5 1059.36  3825.6 1055.31  4145.1 1052.09    4514 1043.84
    4649 1037.85    4727 1030.61  4754.6 1025.74    4840  1019.6  4854.3 1016.21
  4868.6 1015.13  4911.4 1015.63  4981.5 1013.63  4982.8 1012.83    5039 1013.63
  5059.6 1020.43  5081.6 1021.24    5131 1027.67  5180.4 1029.19  5237.5 1027.37
  5352.5 1033.33  5384.2 1033.67  5522.6 1036.46  5630.3 1039.39  5716.1    1044
  5795.4 1052.75  5826.3 1059.34  5886.8 1068.35  5905.6  1069.9    6032 1098.47
#Mann= 6 ,-1 , 0
  3491.1     .05       0  4981.5     .05       0    5039     .05       0
  5384.2     .12       0  5522.6     .05       0  5886.8     .12       0
Bank Sta=4981.5,5039
XS Rating Curve= 0 ,0
Exp/Cntr=0.3,0.1

Type RM Length L Ch R = 1 ,9988    ,615,615,615
BEGIN DESCRIPTION:
COAL CREEK 17.0
END DESCRIPTION:
XS GIS Cut Line= 3
      2841956.89     10156987.71      2842992.12     10156203.91
      2843955.71     10155253.09
#Sta/Elev= 30
  3436.6 1060.08  3667.5 1052.97  3738.3 1053.07  3781.9 1049.75  3874.1 1049.78
    4017 1044.85    4067 1040.53  4225.1  1037.7  4237.8 1040.05  4281.3 1040.34
  4310.4 1037.93  4381.1 1039.54  4410.3 1037.51  4438.5 1040.21  4630.8 1042.49
  4866.3 1028.33  4914.9 1018.31  4973.6 1014.44  5055.9  1013.6  5057.3  1012.8
  5113.4  1013.6  5176.5 1014.27    5268 1024.71  5449.4  1032.7  5526.9 1035.31
  5643.3 1038.72  5706.2 1043.16  5868.3 1055.65  6018.1 1076.44  6088.8 1091.55
#Mann= 10 ,-1 , 0
  3436.6     .05       0  4866.3     .12       0  4973.6     .05       0
  5055.9     .05       0  5113.4     .05       0    5268     .12       0
  5449.4     .05       0  5526.9     .12       0  5706.2     .05       0
  5868.3     .12       0
Bank Sta=5055.9,5113.4
XS Rating Curve= 0 ,0
Exp/Cntr=0.3,0.1

Type RM Length L Ch R = 1 ,9373    ,380,380,380
BEGIN DESCRIPTION:
COAL CREEK 16.0
END DESCRIPTION:
XS GIS Cut Line= 3
       2842884.7     10157496.86      2844019.99     10155824.23
      2844585.57     10155391.11
#Sta/Elev= 30
  3784.1 1078.49  3830.6 1077.09  3909.5 1069.37  4118.1 1060.34  4234.8 1050.64
  4347.4 1045.87  4651.1 1031.57    4681 1028.03  4755.2 1028.44  4907.1 1025.67
  4953.5 1023.57  4974.5 1018.02  4975.6 1007.81    4977 1007.01  5033.2 1007.81
  5092.3 1012.68  5408.1 1017.35  5486.5 1027.24  5608.1 1030.12  5911.6 1040.88
    5964 1043.26    6061  1048.4  6132.3  1054.7  6199.8 1061.41  6295.2 1073.24
  6445.1 1098.63  6473.8 1101.17  6488.3 1105.78  6505.3 1104.99    6518 1104.06
#Mann= 15 ,-1 , 0
  3784.1     .05       0  4347.4     .12       0  4755.2     .05       0
  4907.1     .12       0  4975.6     .07       0  5033.2     .12       0
  5092.3     .05       0  5608.1     .12       0  5911.6     .05       0
    5964     .12       0    6061     .05       0  6132.3     .12       0
  6199.8     .05       0  6445.1     .12       0  6505.3     .05       0
Bank Sta=4975.6,5033.2
XS Rating Curve= 0 ,0
Exp/Cntr=0.3,0.1

Type RM Length L Ch R = 1 ,8993    ,1275,1275,1275
BEGIN DESCRIPTION:
COAL CREEK 15.0
END DESCRIPTION:
XS GIS Cut Line= 3
      2843500.56     10157291.54      2844223.14     10156174.83
      2844632.77     10155576.76
#Sta/Elev= 30
  4310.8 1065.16  4431.5 1056.06  4499.1 1053.28  4515.4  1054.9  4624.3 1053.32
  4754.2 1045.95  4841.9 1036.42  4892.6 1033.35  4913.9 1029.76  4928.3 1026.81
  4941.5 1019.28    4943 1007.46  4944.4 1006.66  5000.6 1007.46  5065.5 1008.46
  5095.6 1011.21  5153.2 1014.32  5355.7 1014.72  5506.7 1018.02  5521.9 1019.28
    5549 1025.33  5579.3 1027.66  5812.7 1031.06  5923.8 1035.64    6016 1044.17
  6062.3 1049.46    6249 1073.45  6291.4 1080.44  6306.3 1086.01  6365.8 1098.85
#Mann= 10 ,-1 , 0
  4310.8     .05       0  4431.5     .12       0  4499.1     .05       0
  4913.9     .12       0    4943     .07       0  5000.6     .12       0
  5095.6     .05       0  5812.7     .12       0    6016     .05       0
  6062.3     .12       0
Bank Sta=4943,5000.6
XS Rating Curve= 0 ,0
Exp/Cntr=0.3,0.1

Type RM Length L Ch R = 1 ,7718    ,664,664,664
BEGIN DESCRIPTION:
COAL CREEK 13.0
END DESCRIPTION:
XS GIS Cut Line= 3
      2843787.99     10157192.99      2844800.06     10156797.89
      2845766.86     10156281.55
#Sta/Elev= 30
    3592  1047.4  3738.7 1037.22  3822.9 1034.75  4124.4 1036.91  4268.3 1035.92
  4694.9 1023.99  4730.2 1019.62  4752.9 1014.26  4848.5 1007.81  5011.5 1003.41
  5012.9 1002.51  5069.2 1003.41  5070.3 1012.94  5093.7    1027  5128.2 1048.32
  5144.5 1052.88  5150.1 1056.56  5160.8 1057.31  5166.4 1060.16  5182.7 1061.06
  5188.4 1064.15    5263 1063.97  5360.1 1058.32  5424.2 1057.31  5506.3 1062.53
  5550.2 1066.61  5666.9  1085.3  5720.1 1091.22  5758.4 1097.92  5774.5 1098.25
#Mann= 6 ,-1 , 0
    3592     .05       0  5011.5     .03       0  5069.2     .05       0
  5093.7     .12       0  5360.1     .05       0  5666.9     .12       0
Bank Sta=5011.5,5069.2
XS Rating Curve= 0 ,0
Exp/Cntr=0.3,0.1

Type RM Length L Ch R = 1 ,7054    ,535,535,535
BEGIN DESCRIPTION:
COAL CREEK 12.0
END DESCRIPTION:
XS GIS Cut Line= 3
      2843714.04     10157299.75      2844932.58     10157147.77
      2845528.75     10157521.48
#Sta/Elev= 30
  3526.6 1049.29  3617.3 1043.52  3622.3 1044.42    3698  1036.2  3713.2  1035.7
  3813.2 1031.43  3921.3 1028.69  4213.3 1026.98  4413.3 1022.89  4513.3  1021.3
  4697.2    1020  4727.5 1019.05  4768.7 1015.07  4781.9 1013.44  4840.9 1012.81
  4884.6 1005.51  4977.2 1001.56  4978.6 1000.66  5034.9 1001.56  5036.6 1008.26
  5073.2 1015.59  5094.4 1017.46  5109.7 1020.68  5146.2 1024.24  5152.1  1023.5
  5246.4 1037.71  5298.2 1041.97  5377.2 1052.58  5407.4 1055.19  5458.2 1057.19
#Mann= 9 ,-1 , 0
  3526.6     .05       0  3713.2     .12       0  3813.2     .05       0
  4213.3     .12       0  4413.3     .05       0  4513.3     .12       0
  4768.7     .05       0  4977.2     .05       0  5034.9     .05       0
Bank Sta=4977.2,5034.9
XS Rating Curve= 0 ,0
Exp/Cntr=0.3,0.1

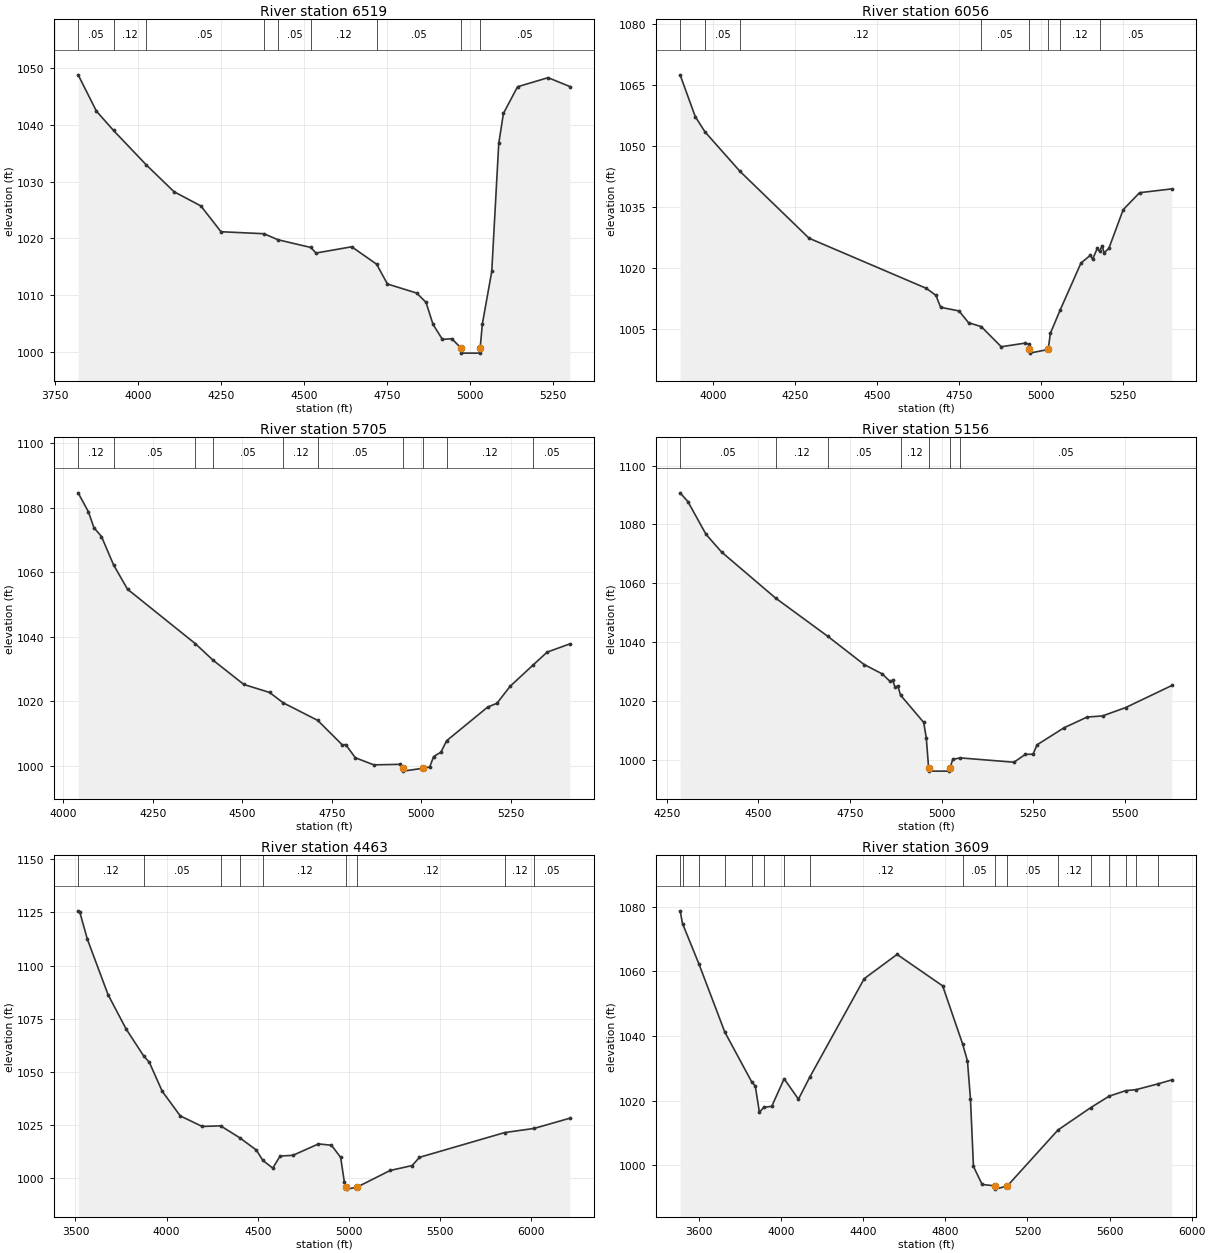
Type RM Length L Ch R = 1 ,6519    ,463,463,463
BEGIN DESCRIPTION:
COAL CREEK 11.0
END DESCRIPTION:
XS GIS Cut Line= 3
      2843689.38     10157390.07      2844632.09     10157520.63
      2845011.03     10157890.59
#Sta/Elev= 30
    3819 1048.81  3874.2 1042.41  3925.6 1039.02  4024.6 1032.94    4108 1028.23
  4188.8 1025.73  4249.4 1021.19  4378.7 1020.84  4420.9 1019.78    4520 1018.42
  4535.4 1017.44  4643.1 1018.54  4718.1 1015.48  4750.7 1011.99  4838.6  1010.4
  4866.9 1008.77  4888.1 1004.88  4916.4 1002.23  4944.6 1002.36  4972.4 1000.72
  4973.7  999.82  5028.7  999.82  5030.1 1000.72  5036.7 1004.96    5065  1014.2
  5086.1 1036.75  5100.2 1042.02  5142.7 1046.71  5234.7 1048.31  5300.3 1046.75
#Mann= 9 ,-1 , 0
    3819     .05       0  3925.6     .12       0  4024.6     .05       0
  4378.7     .12       0  4420.9     .05       0    4520     .12       0
  4718.1     .05       0  4972.4     .05       0  5030.1     .05       0
Bank Sta=4972.4,5030.1
XS Rating Curve= 0 ,0
Exp/Cntr=0.3,0.1

Type RM Length L Ch R = 1 ,6056    ,351,351,351
BEGIN DESCRIPTION:
COAL CREEK 10.0
END DESCRIPTION:
XS GIS Cut Line= 3
      2843410.27     10157562.51      2844099.97      10157702.1
      2844731.43     10158185.94
#Sta/Elev= 30
  3899.1  1067.6  3945.4 1057.32    3975 1053.58  4081.6 1043.88  4292.3 1027.43
  4649.8 1015.11  4678.9 1013.39  4693.4 1010.45  4749.5 1009.55  4778.6 1006.65
  4817.1 1005.71  4878.3 1000.75  4950.1 1001.63  4963.5 1001.38  4963.7 1000.08
    4965  999.18  5021.4 1000.08  5027.9 1004.05  5057.9 1009.79  5121.3 1021.33
  5150.3 1023.26  5156.6 1022.24  5171.1 1024.96  5178.3 1024.17  5185.7 1025.59
    5192 1023.82  5206.5 1024.97    5250 1034.45  5299.9 1038.62  5398.3 1039.56
#Mann= 8 ,-1 , 0
  3899.1     .12       0    3975     .05       0  4081.6     .12       0
  4817.1     .05       0  4963.7     .05       0  5021.4     .05       0
  5057.9     .12       0  5178.3     .05       0
Bank Sta=4963.7,5021.4
XS Rating Curve= 0 ,0
Exp/Cntr=0.3,0.1

Type RM Length L Ch R = 1 ,5705    ,549,549,549
BEGIN DESCRIPTION:
COAL CREEK 9.0
END DESCRIPTION:
XS GIS Cut Line= 3
      2843305.67      10157603.1      2844113.25       10158119.
      2844505.67     10158253.11
#Sta/Elev= 30
  4041.7 1084.59  4070.5  1078.7  4085.7 1073.81  4106.9 1071.06  4140.8 1062.24
  4179.6 1054.74  4368.8 1037.88  4418.2 1032.77  4504.5 1025.22  4576.4 1022.75
  4613.9 1019.57  4710.9 1014.08  4779.4 1006.49  4788.7 1006.61  4815.8 1002.52
  4867.4 1000.32  4940.1 1000.49  4947.6  999.28    4949  998.38  5005.3  999.28
  5023.3  999.65  5034.3 1002.89  5054.6 1004.25  5070.6  1007.8  5185.2 1018.22
  5211.2  1019.4  5247.8 1024.65    5312 1031.25  5351.3 1035.25  5414.7  1037.8
#Mann= 10 ,-1 , 0
  4041.7     .12       0  4140.8     .05       0  4368.8     .12       0
  4418.2     .05       0  4613.9     .12       0  4710.9     .05       0
  4947.6     .05       0  5005.3     .05       0  5070.6     .12       0
    5312     .05       0
Bank Sta=4947.6,5005.3
XS Rating Curve= 0 ,0
Exp/Cntr=0.3,0.1

Type RM Length L Ch R = 1 ,5156    ,693,693,693
BEGIN DESCRIPTION:
COAL CREEK 8.0
END DESCRIPTION:
XS GIS Cut Line= 3
      2843105.72     10157803.14      2843607.75       10158310.
      2844205.64      10158503.1
#Sta/Elev= 30
  4286.6 1090.75  4307.8 1087.78  4357.2 1076.66  4399.7 1070.63  4546.9 1054.98
  4689.4 1041.97  4788.6 1032.37  4838.1 1029.18  4859.3 1026.63  4866.4    1027
  4873.5 1024.56  4880.5 1025.14    4888 1021.97  4951.2 1012.69  4958.3 1007.45
  4964.8  997.01  4966.2  996.11  5021.2  996.11  5022.6  997.01  5030.5 1000.12
  5051.3 1000.61  5197.5  999.14    5229 1001.83  5249.5 1001.85  5260.5 1005.05
  5334.1 1010.85  5397.2  1014.5  5439.2 1014.88  5502.2 1017.72  5628.3 1025.23
#Mann= 7 ,-1 , 0
  4286.6     .05       0  4546.9     .12       0  4689.4     .05       0
    4888     .12       0  4964.8     .07       0  5022.6     .12       0
  5051.3     .05       0
Bank Sta=4964.8,5022.6
XS Rating Curve= 0 ,0
Exp/Cntr=0.3,0.1

Type RM Length L Ch R = 1 ,4463    ,854,854,854
BEGIN DESCRIPTION:
Mapping XS 36b6c44b
END DESCRIPTION:
XS GIS Cut Line= 4
      2841997.92     10159377.17      2842539.86     10158802.39
      2843787.95     10158933.77      2844329.89     10158572.47
#Sta/Elev= 30
  3514.6 1125.71  3522.8 1125.38  3565.3 1112.36  3678.6 1086.35  3777.7 1070.19
  3873.2 1057.64    3905 1054.53  3975.6 1040.95  4074.7 1029.35  4194.8  1024.4
  4296.1 1024.68  4400.3  1019.1  4491.4 1013.34  4527.4 1008.44  4581.9 1004.82
  4622.1 1010.49  4692.5 1010.84  4832.6 1016.19  4903.7 1015.58    4954 1009.88
  4974.1  998.41  4985.4  995.85  4986.8  994.95  5043.2  995.85  5225.5 1003.72
  5346.1 1006.03  5386.3 1009.89  5853.2 1021.52  6015.9 1023.49  6210.9 1028.28
#Mann= 9 ,-1 , 0
  3514.6     .12       0  3873.2     .05       0  4296.1     .12       0
  4400.3     .05       0  4527.4     .12       0  4985.4     .07       0
  5043.2     .12       0  5853.2     .12       0  6015.9     .05       0
Bank Sta=4985.4,5043.2
XS Rating Curve= 0 ,0
Exp/Cntr=0.3,0.1

Type RM Length L Ch R = 1 ,3609    ,420,420,420
BEGIN DESCRIPTION:
COAL CREEK 6.0
END DESCRIPTION:
XS GIS Cut Line= 3
      2842399.67     10159727.71       2843533.4     10159672.77
      2844288.83      10158662.8
#Sta/Elev= 30
  3507.1 1078.78    3519 1074.83    3599 1062.29  3724.9 1041.23  3855.2 1025.89
  3873.5  1024.5  3893.6 1016.37  3915.1 1017.91  3953.6 1018.21  4014.2 1026.75
  4083.8 1020.43  4138.3 1027.18  4404.2 1057.75  4564.4 1065.28  4786.6 1055.53
  4883.9 1037.52  4907.5 1032.27  4922.1 1020.45  4936.7  999.58  4978.9  994.01
  5042.3  993.56  5043.8  992.56  5101.9  993.56  5348.5 1010.88  5508.3 1017.82
  5597.5 1021.35  5678.4 1023.06  5730.5  1023.4  5835.4 1025.16  5903.4  1026.4
#Mann= 17 ,-1 , 0
  3507.1     .05       0    3519     .12       0    3599     .05       0
  3724.9     .12       0  3855.2     .05       0  3915.1     .12       0
  4014.2     .05       0  4138.3     .12       0  4883.9     .05       0
  5042.3     .05       0  5101.9     .05       0  5348.5     .12       0
  5508.3     .05       0  5597.5     .12       0  5678.4     .05       0
  5730.5     .12       0  5835.4     .05       0
Bank Sta=5042.3,5101.9
XS Rating Curve= 0 ,0
Exp/Cntr=0.3,0.1

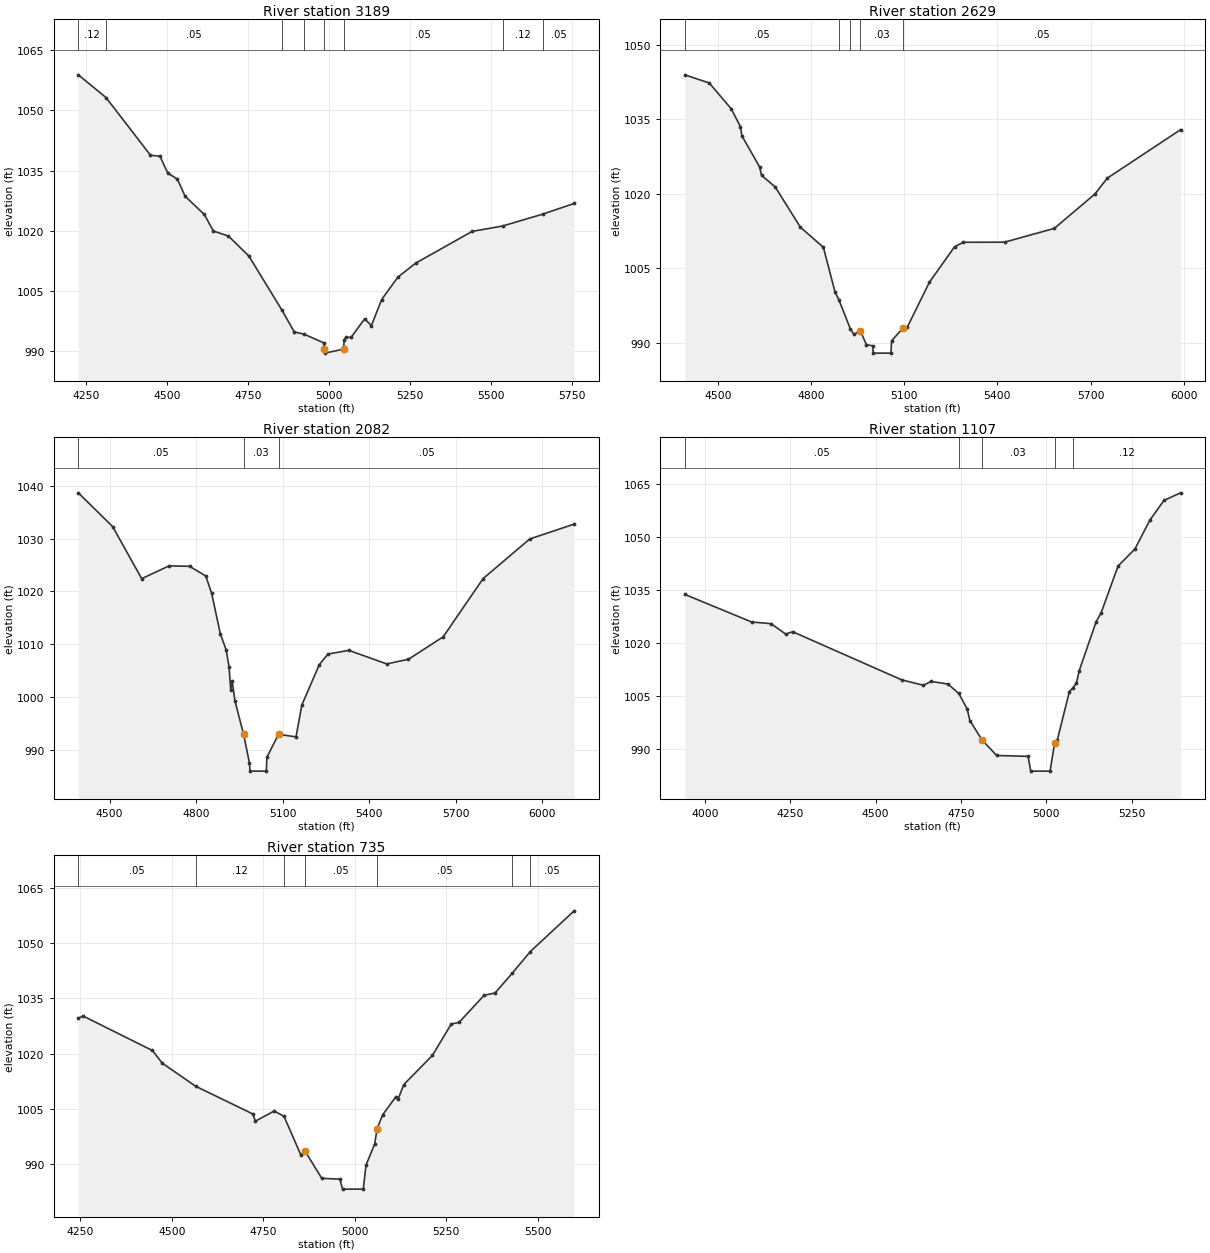
Type RM Length L Ch R = 1 ,3189    ,560,560,560
BEGIN DESCRIPTION:
COAL CREEK 5.0
END DESCRIPTION:
XS GIS Cut Line= 3
      2843656.61     10159902.66      2844045.06     10159745.03
      2844387.26     10158687.75
#Sta/Elev= 30
  4225.7 1058.86  4311.2 1053.19  4448.3 1038.82  4477.7 1038.56  4501.8 1034.37
  4531.3 1032.87  4555.4 1028.58  4614.4 1024.06  4642.6 1019.92    4689 1018.67
    4752 1013.69    4854 1000.22  4892.2  994.77  4922.4  994.21    4983  992.05
    4985  990.48  4986.5  989.48  5044.6  990.48  5046.3  992.78  5052.2  993.47
  5067.4  993.38  5109.4  998.02  5130.4  996.35    5162 1002.84  5212.3 1008.44
  5267.1 1011.92  5441.5 1019.83  5535.4 1021.17  5658.7 1024.12  5756.2 1026.79
#Mann= 8 ,-1 , 0
  4225.7     .12       0  4311.2     .05       0    4854     .12       0
  4922.4     .05       0    4985     .05       0  5044.6     .05       0
  5535.4     .12       0  5658.7     .05       0
Bank Sta=4985,5044.6
XS Rating Curve= 0 ,0
Exp/Cntr=0.3,0.1

Type RM Length L Ch R = 1 ,2629    ,547,547,547
BEGIN DESCRIPTION:
COAL CREEK 4.0
END DESCRIPTION:
XS GIS Cut Line= 3
      2844592.64      10160140.8      2844740.44     10159188.31
      2844715.84     10158557.08
#Sta/Elev= 30
  4394.1 1043.91  4472.7 1042.27  4543.6 1037.07  4572.9  1033.5    4578 1031.61
  4634.6 1025.41    4641 1023.69  4685.2 1021.33  4766.2 1013.23    4840 1009.21
  4877.5 1000.21  4890.3  998.58  4926.4  992.85  4938.2  991.67  4958.5   992.4
  4978.7   989.6  4998.9  989.38  5000.5   987.9  5057.2   987.9  5059.7  990.39
  5096.9     993  5110.3  993.15  5181.1 1002.15  5262.1  1009.3  5290.9 1010.21
  5423.2 1010.23  5583.4 1013.01  5713.5  1019.9  5753.5  1023.1  5989.7 1032.88
#Mann= 5 ,-1 , 0
  4394.1     .05       0  4890.3     .12       0  4926.4     .05       0
  4958.5     .03       0  5096.9     .05       0
Bank Sta=4958.5,5096.9
XS Rating Curve= 0 ,0
Exp/Cntr=0.3,0.1

Type RM Length L Ch R = 1 ,2082    ,975,975,975
BEGIN DESCRIPTION:
COAL CREEK 3.0
END DESCRIPTION:
XS GIS Cut Line= 3
      2845274.16     10160140.82      2845150.99     10159262.21
      2844838.98     10158490.39
#Sta/Elev= 30
  4391.8 1038.63  4510.7 1032.26  4611.6 1022.42  4706.3 1024.83  4777.6 1024.76
  4833.8 1022.92    4854 1019.69  4884.3 1012.01  4904.5 1008.96  4914.6 1005.73
  4920.3 1001.41  4925.4 1003.09  4934.8  999.38  4965.1  992.99  4985.3  987.61
  4987.2  986.07  5043.9  986.07  5045.8   988.7  5086.2  993.02  5146.8  992.54
    5167  998.56  5227.6 1006.19  5257.9 1008.19  5329.9 1008.88  5461.3 1006.32
  5536.9  1007.2  5657.2 1011.43  5795.8 1022.44  5957.6 1029.92  6111.5 1032.72
#Mann= 3 , 0 , 0
  4391.8     .05       0  4965.1     .03       0  5086.2     .05       0
Bank Sta=4965.1,5086.2
XS Rating Curve= 0 ,0
Exp/Cntr=0.3,0.1

Type RM Length L Ch R = 1 ,1107    ,372,372,372
BEGIN DESCRIPTION:
COAL CREEK 2.0
END DESCRIPTION:
XS GIS Cut Line= 3
      2845356.28     10160050.47      2845799.67     10159541.39
      2846284.12     10158933.78
#Sta/Elev= 30
  3941.4 1033.65  4137.1 1025.85  4194.1 1025.37  4236.8 1022.44  4257.7 1023.08
  4576.7 1009.48  4640.2 1007.95  4662.7 1009.04  4712.3 1008.29  4743.7 1005.64
  4768.3 1001.31  4776.4  997.96  4811.6  992.54  4854.8  988.09  4946.8  987.85
  4954.6  983.67  5011.3  983.67  5024.6  991.66  5032.6  992.55  5067.8 1006.15
  5078.5 1007.26  5088.6 1008.59  5096.6 1012.08  5146.3 1025.96  5160.7  1028.4
  5210.3 1041.67    5260 1046.53  5303.2  1054.6  5344.8 1060.24  5393.6 1062.38
#Mann= 5 ,-1 , 0
  3941.4     .05       0  4743.7     .12       0  4811.6     .03       0
  5024.6     .05       0  5078.5     .12       0
Bank Sta=4811.6,5024.6
XS Rating Curve= 0 ,0
Exp/Cntr=0.3,0.1

Type RM Length L Ch R = 1 ,735     ,0,0,0
BEGIN DESCRIPTION:
COAL CREEK 1.0
END DESCRIPTION:
XS GIS Cut Line= 3
      2845594.39     10159960.16      2846514.04     10159368.96
      2846522.22     10159107.17
#Sta/Elev= 30
  4244.8 1029.65  4258.2 1030.19  4447.2 1020.84  4474.3 1017.39  4565.5 1011.12
  4721.9 1003.58  4728.6 1001.62  4780.1 1004.39  4806.9 1002.96  4852.6  992.53
  4864.6  993.46  4910.2  986.09  4959.6  985.88  4966.9  983.16  5023.6  983.16
  5031.1  989.68  5054.7  995.41  5061.5  999.63  5076.7 1003.38    5113 1008.31
  5118.9 1007.64  5134.1 1011.55  5212.7 1019.52  5264.2 1028.05  5285.4 1028.48
  5353.9 1035.83    5384 1036.49  5430.1 1041.77  5480.3 1047.74    5600  1058.8
#Mann= 7 ,-1 , 0
  4244.8     .05       0  4565.5     .12       0  4806.9     .05       0
  4864.6     .05       0  5061.5     .05       0  5430.1     .12       0
  5480.3     .05       0
Bank Sta=4864.6,5061.5
XS Rating Curve= 0 ,0
Exp/Cntr=0.3,0.1

Chan Stop Cuts=-1
Use User Specified Reach Order=0
Composite Channel Slope=5