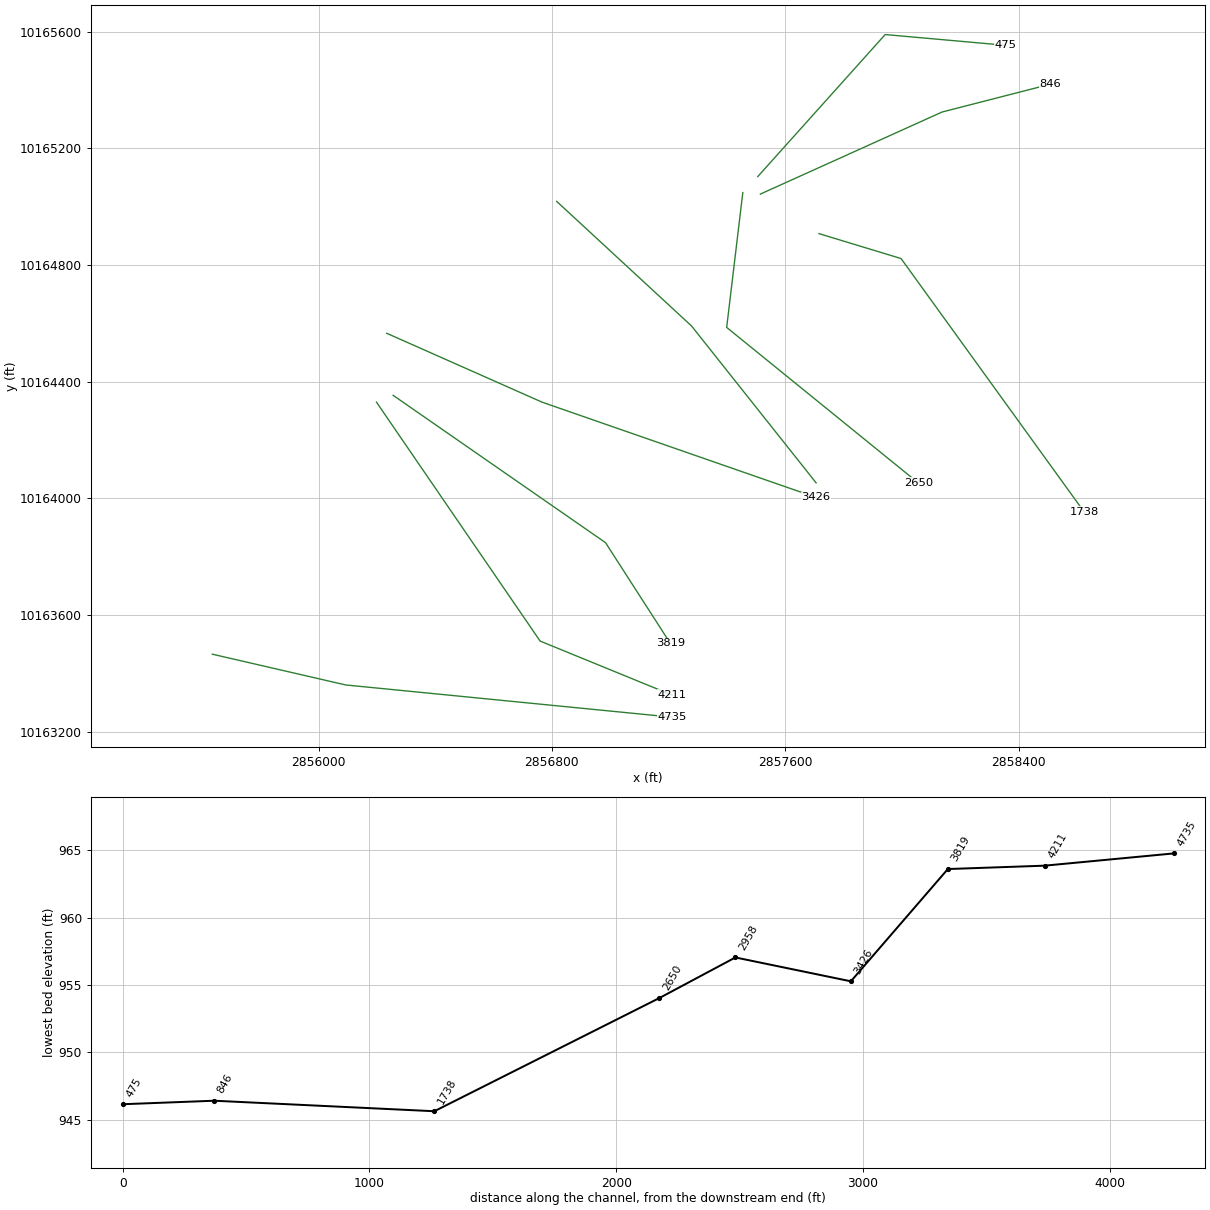
HEC-RAS study COMANCHE CREEK.prj: COMANCHE CREEK Base Level Engineering

--- COMANCHE CREEK.g01 (geometry) --- (continued)

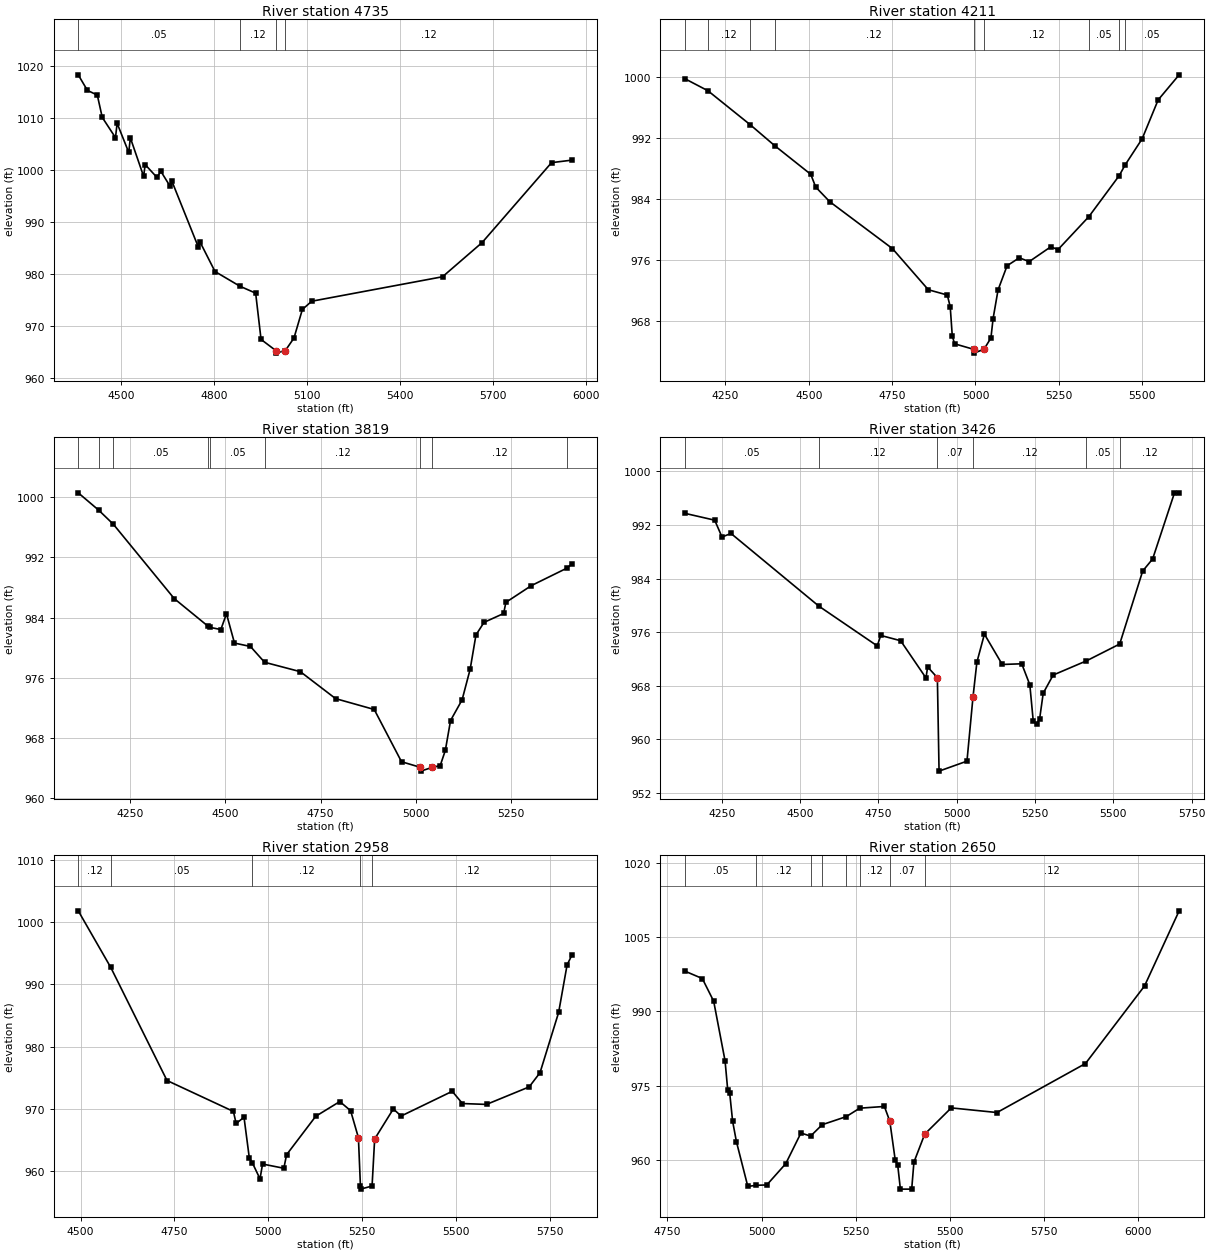
Type RM Length L Ch R = 1 ,4735    ,524,524,524
BEGIN DESCRIPTION:
COMANCHE CREEK 9.0
END DESCRIPTION:
XS GIS Cut Line= 3
       2855635.8     10163465.68      2856092.95     10163360.18
      2857211.96     10163249.79
#Sta/Elev= 30
    4363 1018.22  4392.6 1015.23  4424.5 1014.33  4440.5 1010.04  4483.2 1006.15
  4488.4 1008.92    4526 1003.31  4531.1 1006.13  4573.9  998.72    4579 1000.97
  4616.7  998.53  4629.7  999.67  4659.4  996.81  4664.6  997.87  4750.1  985.19
  4755.2   986.2  4804.2  980.44  4884.7  977.61  4935.4  976.28  4952.8  967.39
  5000.3  965.26  5000.8  964.76  5031.2  965.26    5059  967.66  5086.1  973.15
  5116.3  974.73  5538.3  979.43    5666     986    5890 1001.35  5956.6 1001.84
#Mann= 4 ,-1 , 0
    4363     .05       0  4884.7     .12       0  5000.3     .07       0
  5031.2     .12       0
Bank Sta=5000.3,5031.2
XS Rating Curve= 0 ,0
Exp/Cntr=0.3,0.1

Type RM Length L Ch R = 1 ,4211    ,392,392,392
BEGIN DESCRIPTION:
COMANCHE CREEK 8.0
END DESCRIPTION:
XS GIS Cut Line= 3
      2856198.47     10164329.72       2856759.5     10163510.64
        2857212.     10163325.52
#Sta/Elev= 30
  4129.2  999.72  4197.3  998.17  4324.3  993.72  4397.8  990.98  4505.8  987.24
  4520.7  985.57  4562.7  983.66  4750.9  977.52  4858.5  972.14  4915.4  971.45
  4924.2  969.92  4930.3  966.12  4937.2  965.07  4994.4  964.35  4994.9  963.85
  5025.4  964.35  5046.3  965.83  5052.8  968.37  5067.7  972.12  5094.8  975.28
  5131.4  976.32  5161.1  975.82  5225.9  977.76  5247.5  977.39  5340.2  981.71
  5431.2  987.07  5448.8  988.46  5499.9  991.88  5547.9  996.97  5610.9 1000.25
#Mann= 9 ,-1 , 0
  4129.2     .05       0  4197.3     .12       0  4324.3     .05       0
  4397.8     .12       0  4994.4     .07       0  5025.4     .12       0
  5340.2     .05       0  5431.2     .12       0  5448.8     .05       0
Bank Sta=4994.4,5025.4
XS Rating Curve= 0 ,0
Exp/Cntr=0.3,0.1

Type RM Length L Ch R = 1 ,3819    ,393,393,393
BEGIN DESCRIPTION:
COMANCHE CREEK 7.0
END DESCRIPTION:
XS GIS Cut Line= 3
       2856255.7      10164353.1      2856983.75       10163848.
      2857205.67     10163503.13
#Sta/Elev= 30
  4113.9 1000.57  4167.5  998.27  4206.3  996.38  4365.8  986.52    4454  982.87
  4460.3  982.69  4488.1  982.41  4502.9   984.5  4523.9  980.61  4565.8  980.16
  4602.9  978.06  4696.8  976.81  4789.3  973.23  4890.6  971.79  4962.2  964.85
    5012   964.1  5012.5   963.6    5043   964.1  5063.8  964.34  5077.2  966.35
  5090.9  970.32  5121.2  973.07  5142.4  977.15  5157.6  981.69  5178.7  983.36
  5230.2  984.54  5236.1  986.02  5302.8  988.24    5396  990.56  5410.1  991.15
#Mann= 9 ,-1 , 0
  4113.9     .05       0  4167.5     .12       0  4206.3     .05       0
    4454     .12       0  4460.3     .05       0  4602.9     .12       0
    5012     .07       0    5043     .12       0    5396     .05       0
Bank Sta=5012,5043
XS Rating Curve= 0 ,0
Exp/Cntr=0.3,0.1

Type RM Length L Ch R = 1 ,3426    ,468,468,468
BEGIN DESCRIPTION:
COMANCHE CREEK 6.0
END DESCRIPTION:
XS GIS Cut Line= 3
       2856233.6     10164565.86      2856766.12     10164329.74
      2857705.65     10164003.12
#Sta/Elev= 30
    4133  993.71  4227.2   992.7  4250.5  990.19  4279.2  990.72  4559.8  979.88
  4746.2  973.95  4757.4  975.51  4820.9  974.72  4901.8  969.17  4907.1  970.81
  4938.2  969.21  4943.6  955.27  5032.7  956.76    5052  966.35  5064.4  971.52
  5088.4   975.7  5145.3  971.18  5207.6  971.28  5233.4  968.15  5244.4  962.71
    5255  962.36  5264.5     963  5276.2   966.9  5307.9   969.6  5414.3  971.72
  5520.4  974.23  5593.8  985.12  5625.5  986.91  5694.7  996.69  5710.2  996.78
#Mann= 6 ,-1 , 0
    4133     .05       0  4559.8     .12       0  4938.2     .07       0
    5052     .12       0  5414.3     .05       0  5520.4     .12       0
Bank Sta=4938.2,5052
XS Rating Curve= 0 ,0
Exp/Cntr=0.3,0.1

Type RM Length L Ch R = 1 ,2958    ,308,308,308
BEGIN DESCRIPTION:
COMANCHE CREEK 5.0
END DESCRIPTION:
XS GIS Cut Line= 3
      2856816.36     10165017.98      2857278.53     10164590.97
      2857705.69      10164053.1
#Sta/Elev= 30
  4493.6 1001.85  4580.3  992.73  4730.1  974.53    4907  969.55  4914.3  967.61
  4935.3  968.61  4949.5  962.03  4957.8  961.24  4977.9  958.69  4984.7  961.08
  5041.4   960.4  5048.7  962.58  5126.4  968.77  5190.5  971.14  5219.3  969.67
  5240.1  965.33  5245.5  957.54    5246  957.04  5276.5  957.54  5283.4  965.11
  5333.1  969.95  5353.9  968.81  5490.1  972.79  5517.3  970.82  5581.4  970.68
  5695.1   973.5    5724  975.79  5773.6  985.49  5796.1  993.14  5809.7  994.81
#Mann= 5 ,-1 , 0
  4493.6     .12       0  4580.3     .05       0  4957.8     .12       0
  5245.5     .07       0  5276.5     .12       0
Bank Sta=5240.1,5283.4
XS Rating Curve= 0 ,0
Exp/Cntr=0.3,0.1

Type RM Length L Ch R = 1 ,2650    ,912,912,912
BEGIN DESCRIPTION:
COMANCHE CREEK 4.0
END DESCRIPTION:
XS GIS Cut Line= 3
      2857454.37     10165048.17       2857399.1     10164585.95
      2858055.69     10164053.11
#Sta/Elev= 30
  4797.1  998.12  4842.5  996.65  4872.7  992.06  4902.9     980  4910.1  973.99
  4915.2  973.47    4923  967.76  4933.1  963.62  4963.3  954.58    4986   954.8
  5013.7  954.88    5064  959.18  5104.3  965.39  5129.9  964.76  5160.8  967.07
  5224.5   968.7  5260.3  970.41  5325.8  970.76  5340.2  967.78  5354.6   959.9
  5361.2  958.88  5368.3  954.03  5398.3  954.03  5404.2  959.48  5432.9  965.16
  5503.3  970.47  5624.7  969.53  5859.6  979.45  6016.3  995.14  6108.2 1010.35
#Mann= 8 ,-1 , 0
  4797.1     .05       0    4986     .12       0  5129.9     .05       0
  5160.8     .12       0  5224.5     .05       0  5260.3     .12       0
  5340.2     .07       0  5432.9     .12       0
Bank Sta=5340.2,5432.9
XS Rating Curve= 0 ,0
Exp/Cntr=0.3,0.1

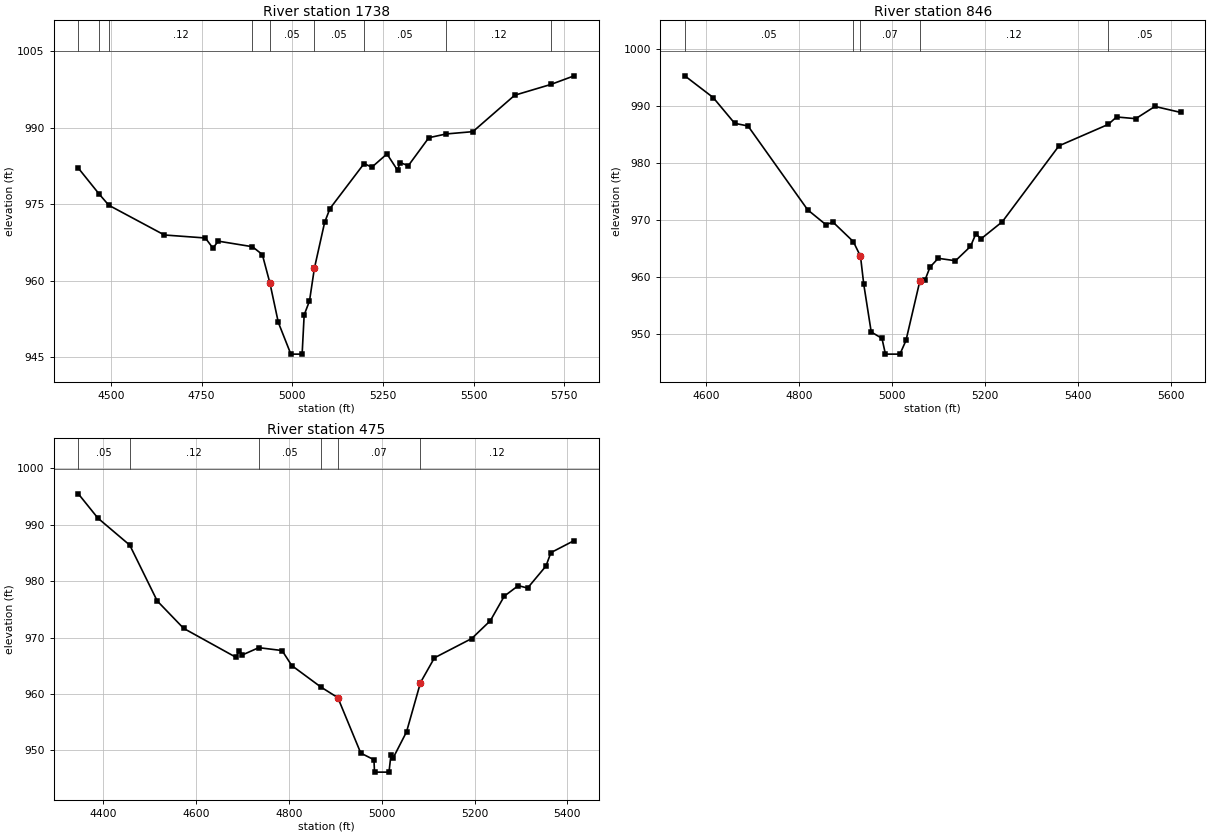
Type RM Length L Ch R = 1 ,1738    ,892,892,892
BEGIN DESCRIPTION:
COMANCHE CREEK 3.0
END DESCRIPTION:
XS GIS Cut Line= 3
      2857715.56     10164907.47      2857996.91     10164822.06
       2858624.9     10163952.93
#Sta/Elev= 30
  4410.5  982.08  4467.9     977  4494.4  974.81  4647.5  968.98  4760.5  968.39
  4781.4  966.41  4796.1  967.77  4890.2  966.68  4917.5  965.15  4938.4  959.56
  4961.6  951.84  4996.1  945.63  5027.2  945.63  5032.8  953.31  5047.5  956.05
    5061  962.45  5089.2  971.45  5103.9  974.16    5198  982.98  5219.2  982.26
    5261  984.86  5290.4  981.64  5296.6  983.18  5319.8  982.56  5376.3  988.04
  5424.3  988.78  5497.7  989.23    5613  996.37    5713  998.49  5776.8 1000.17
#Mann= 9 ,-1 , 0
  4410.5     .12       0  4467.9     .05       0  4494.4     .12       0
  4890.2     .05       0  4938.4     .05       0    5061     .05       0
    5198     .05       0  5424.3     .12       0    5713     .05       0
Bank Sta=4938.4,5061
XS Rating Curve= 0 ,0
Exp/Cntr=0.3,0.1

Type RM Length L Ch R = 1 ,846     ,371,371,371
BEGIN DESCRIPTION:
COMANCHE CREEK 2.0
END DESCRIPTION:
XS GIS Cut Line= 3
      2857514.64      10165043.1      2858137.58     10165324.42
       2858509.3     10165419.87
#Sta/Elev= 30
    4554  995.32  4615.1   991.5  4661.4  986.97    4690  986.51  4818.5  971.77
  4857.3  969.19  4873.4  969.58  4916.7  966.19  4932.2   963.6  4939.2   958.7
  4955.3   950.3  4978.4  949.18  4985.9  946.41  5017.1  946.41  5030.1  948.81
  5059.9  959.24  5070.9   959.4  5081.9  961.71  5099.5  963.25  5136.7  962.82
  5168.9  965.33  5180.6  967.56  5191.6  966.67  5237.5  969.68  5359.5  983.02
  5465.4  986.78  5483.4  988.09  5524.7  987.79  5565.9  989.94  5621.3  988.89
#Mann= 5 ,-1 , 0
    4554     .05       0  4916.7     .12       0  4932.2     .07       0
  5059.9     .12       0  5465.4     .05       0
Bank Sta=4932.2,5059.9
XS Rating Curve= 0 ,0
Exp/Cntr=0.3,0.1

Type RM Length L Ch R = 1 ,475     ,0,0,0
BEGIN DESCRIPTION:
COMANCHE CREEK 1.0
END DESCRIPTION:
XS GIS Cut Line= 3
       2857505.7     10165103.12       2857942.5       10165590.
      2858355.66     10165553.11
#Sta/Elev= 30
  4345.9   995.5  4388.1  991.19  4456.8   986.4    4516   976.5  4572.8  971.65
  4685.6  966.52  4693.1  967.67  4699.8  966.94  4734.9  968.22  4785.1  967.71
    4806  965.05  4868.8  961.24  4905.4  959.35  4954.8  949.52  4983.2  948.35
  4984.4  946.15  5015.6  946.15  5019.7   949.1  5024.8   948.7  5053.4  953.28
  5083.5  962.03  5113.6  966.42    5194  969.84  5234.1     973  5264.2  977.36
  5294.4  979.22  5314.4  978.79  5354.1   982.7  5364.6  985.07  5414.8  987.21
#Mann= 6 ,-1 , 0
  4345.9     .05       0  4456.8     .12       0  4734.9     .05       0
  4868.8     .12       0  4905.4     .07       0  5083.5     .12       0
Bank Sta=4905.4,5083.5
XS Rating Curve= 0 ,0
Exp/Cntr=0.3,0.1

Chan Stop Cuts=-1
Use User Specified Reach Order=0
Composite Channel Slope=5