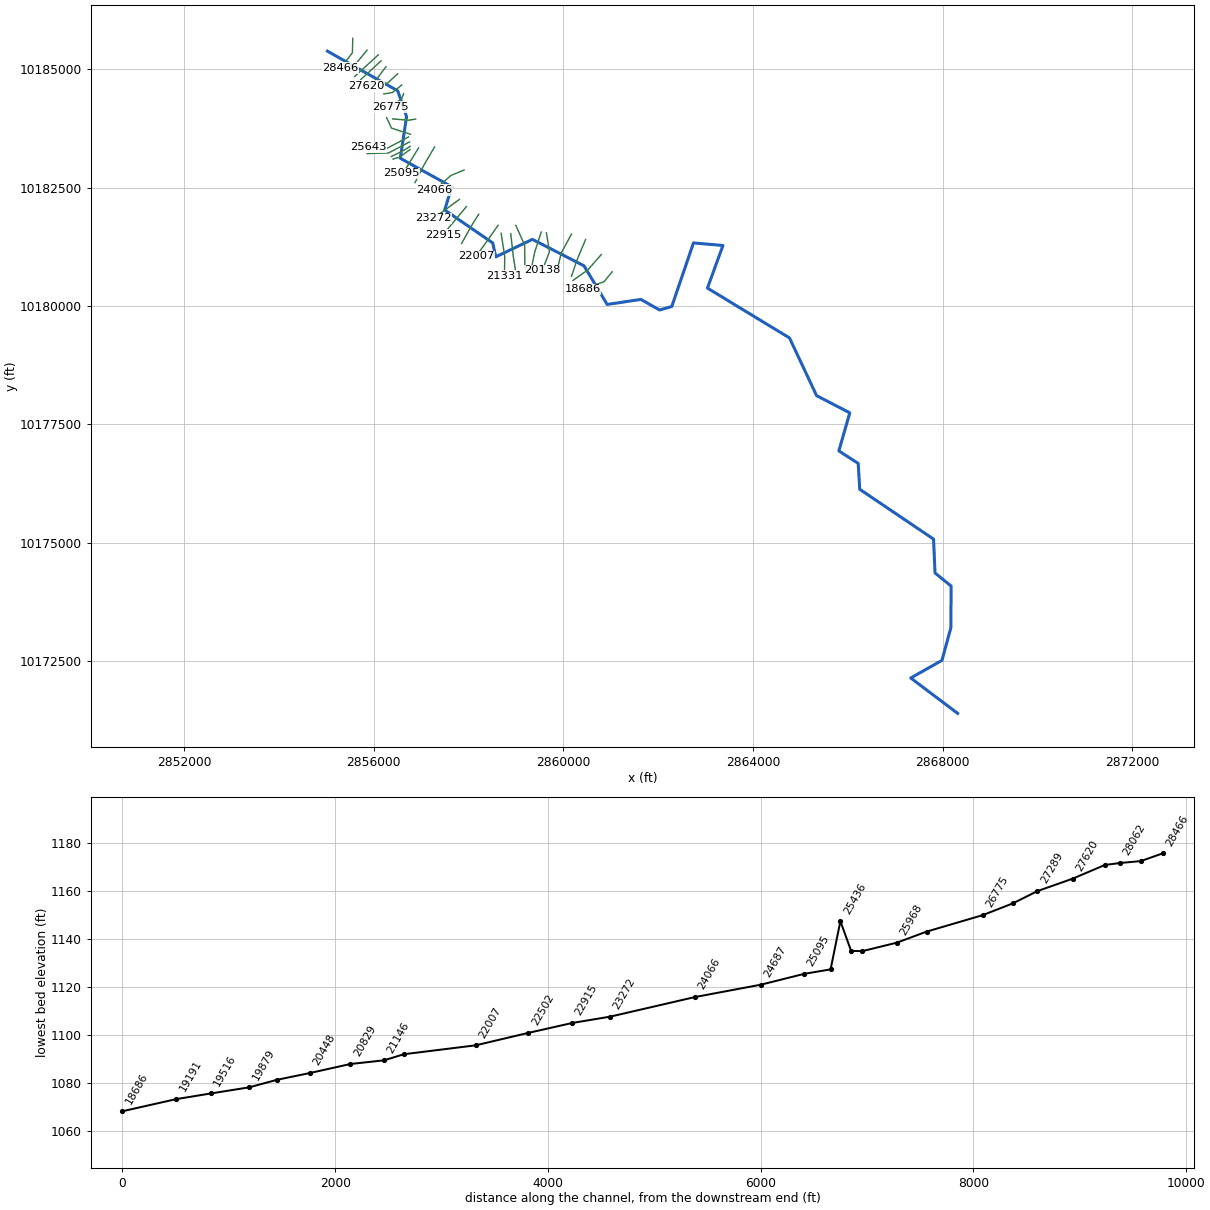
--- COTTONWOOD CREEK 01.prj (project) ---

Proj Title=COTTONWOOD CREEK 01 Base Level Engineering
Current Plan=p01
Default Exp/Contr=0.3,0.1
English Units
Geom File=g01
Flow File=f01
Plan File=p01
BEGIN DESCRIPTION:
COTTONWOOD CREEK 01
END DESCRIPTION:

--- COTTONWOOD CREEK 01.p01 (plan) ---

Plan Title=Multiple Run
Short Identifier=Multiple
Geom File=g01
Flow File=f01
Subcritical Flow
K Sum by GR= 0
Std Step Tol= 0.01
Critical Tol= 0.01
Num of Std Step Trials= 20
Max Error Tol= 0.3
Flow Tol Ratio= 0.001
Split Flow NTrial= 30
Split Flow Tol= 0.02
Split Flow Ratio= 0.02
Log Output Level= 0
Friction Slope Method= 1
Unsteady Friction Slope Method= 2
Unsteady Bridges Friction Slope Method= 1
Parabolic Critical Depth
Global Vel Dist=  1 , 1 , 1
Global Log Level= 0
CheckData=True
Encroach Param= -1, 0, 0, 0
BEGIN DESCRIPTION:
Multiple Run
END DESCRIPTION:

--- COTTONWOOD CREEK 01.f01 (steady flow) ---

Flow Title=Multiple
Number of Profiles=7
Profile Names=10-year,25-year,50-year,1pct_min,100-year,1pct_plu,500-year
River Rch & RM= COTTONWOOD CREEK,Reach-1,28466
     535     885    1891    1426    2705    5131    3997
River Rch & RM= COTTONWOOD CREEK,Reach-1,15281
     796    1348    2996    2247    4342    8393    6378
River Rch & RM= COTTONWOOD CREEK,Reach-1,11648
    1132    1967    4167    2980    6076   12387    8866
River Rch & RM= COTTONWOOD CREEK,Reach-1,3817
    1207    2104    4503    3222    6583   13453    9601
River Rch & RM= COTTONWOOD CREEK,Reach-1,2848
    1511    2661    6045    4394    8924   18124   12977
River Rch & RM= COTTONWOOD CREEK,Reach-1,1062
    1718    3043    7090    5190   10514   21301   15253
Boundary for River Rch & Prof#=COTTONWOOD CREEK,Reach-1,1
Up Type=0
Dn Type=3
Dn Slope=0.005
Boundary for River Rch & Prof#=COTTONWOOD CREEK,Reach-1,2
Up Type=0
Dn Type=3
Dn Slope=0.005
Boundary for River Rch & Prof#=COTTONWOOD CREEK,Reach-1,3
Up Type=0
Dn Type=3
Dn Slope=0.005
Boundary for River Rch & Prof#=COTTONWOOD CREEK,Reach-1,4
Up Type=0
Dn Type=3
Dn Slope=0.005
Boundary for River Rch & Prof#=COTTONWOOD CREEK,Reach-1,5
Up Type=0
Dn Type=3
Dn Slope=0.005
Boundary for River Rch & Prof#=COTTONWOOD CREEK,Reach-1,6
Up Type=0
Dn Type=3
Dn Slope=0.005
Boundary for River Rch & Prof#=COTTONWOOD CREEK,Reach-1,7
Up Type=0
Dn Type=3
Dn Slope=0.005

--- COTTONWOOD CREEK 01.g01 (geometry) ---

Geom Title=Existing Conditions

River Reach=COTTONWOOD CREEK,Reach-1
Reach XY= 30
      2855022.25     10185382.00      2856504.00     10184545.00
      2856690.75     10184000.00      2856558.75     10183120.00
      2857644.75     10182519.00      2857495.50     10182029.00
      2858508.50     10181332.00      2858571.00     10181039.00
      2859345.75     10181408.00      2860434.75     10180849.00
      2860922.25     10180034.00      2861633.00     10180140.00
      2862028.75     10179917.00      2862284.75     10179990.00
      2862743.00     10181333.00      2863364.25     10181279.00
      2863037.50     10180379.00      2864768.25     10179327.00
      2865340.00     10178108.00      2866040.50     10177745.00
      2865809.25     10176941.00      2866217.75     10176677.00
      2866249.75     10176131.00      2867806.75     10175079.00
      2867838.00     10174364.00      2868177.50     10174087.00
      2868172.00     10173208.00      2867984.50     10172519.00
      2867325.75     10172146.00      2868315.50     10171399.00

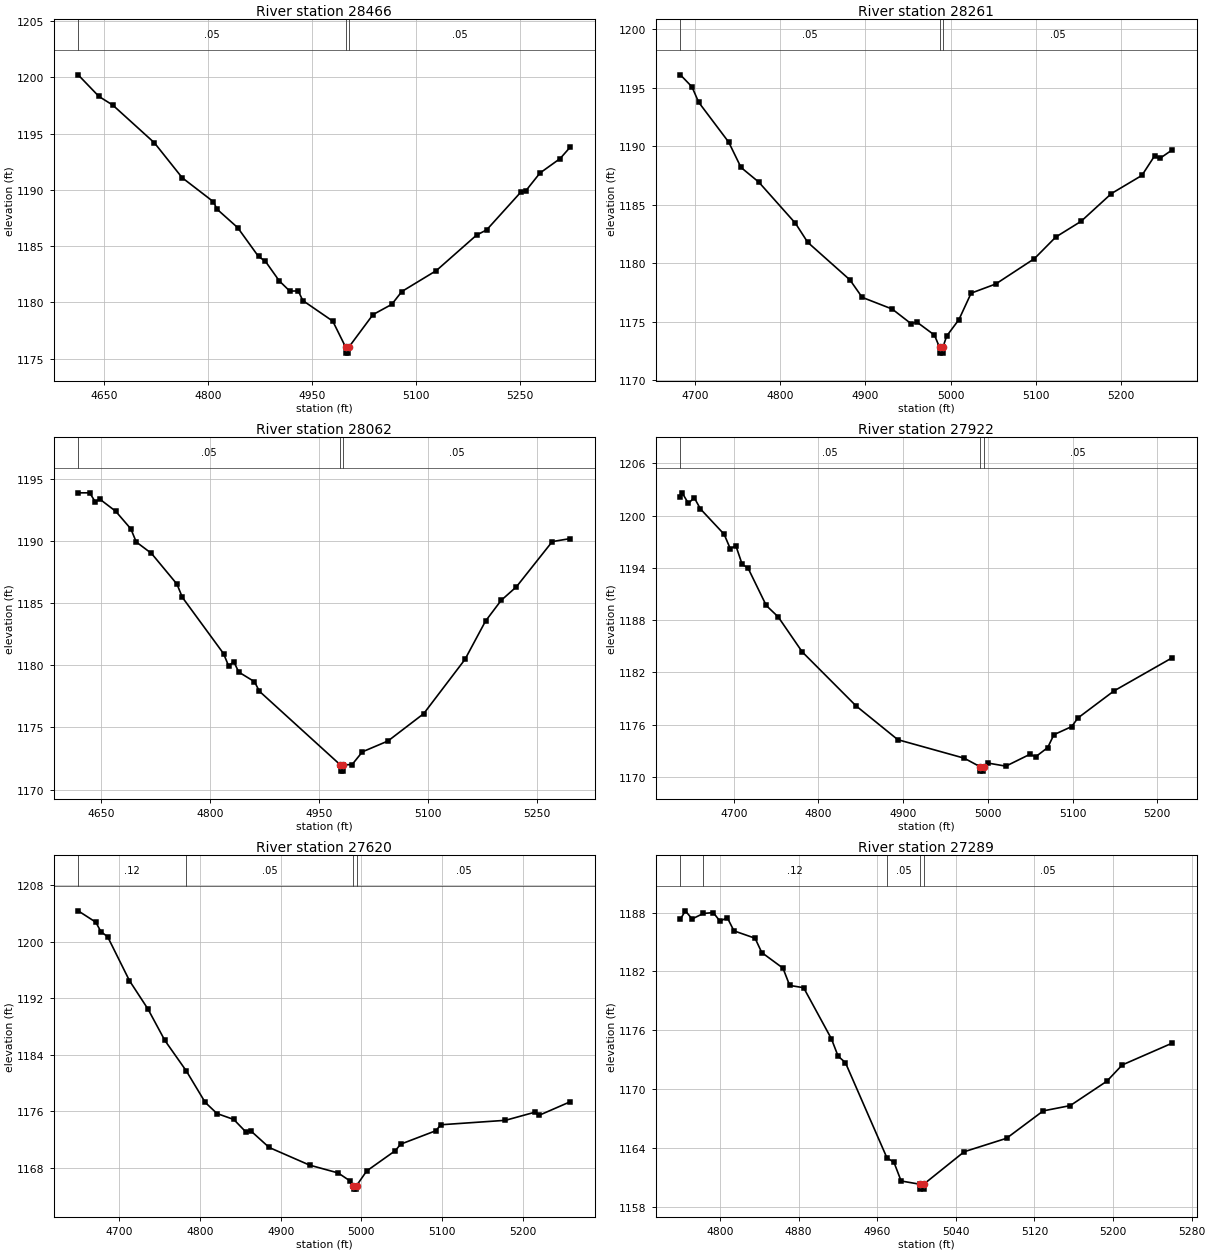
Type RM Length L Ch R = 1,28466,205,205,205
BEGIN DESCRIPTION:
COTTONWOOD CREEK 01 62.0
END DESCRIPTION:
XS GIS Cut Line= 3
      2855555.68     10185653.12      2855547.86     10185347.85
      2855300.58     10185028.20
#Sta/Elev= 30
  4612.7 1200.21  4642.7 1198.29  4662.7 1197.52  4722.7 1194.17  4762.8 1191.07
  4807.8 1188.94  4812.8 1188.29  4842.8 1186.64  4872.8 1184.08  4882.8 1183.65
  4902.8 1181.91  4917.9 1181.01  4930.1 1181.02  4936.7 1180.17  4979.9 1178.34
  4998.7 1176.00  4999.0 1175.50  5002.5 1175.50  5002.7 1176.00  5037.9 1178.92
  5065.0 1179.83  5079.5 1180.97  5129.3 1182.83  5187.3 1185.98  5201.8 1186.44
  5251.6 1189.83  5257.9 1189.88  5278.7 1191.49  5307.7 1192.77  5322.2 1193.78
#Mann=3,-1,0
  4612.7    0.05       0  4998.7    0.05       0  5002.7    0.05       0
Bank Sta=4998.7,5002.7
Exp/Cntr=0.3,0.1

Type RM Length L Ch R = 1,28261,199,199,199
BEGIN DESCRIPTION:
COTTONWOOD CREEK 01 61.0
END DESCRIPTION:
XS GIS Cut Line= 3
      2855855.66     10185403.08      2855593.29     10185081.29
      2855500.10     10184949.02
#Sta/Elev= 30
  4682.9 1196.11  4696.5 1195.08  4704.4 1193.76  4739.6 1190.35  4754.0 1188.19
  4774.8 1186.94  4817.9 1183.41  4832.2 1181.79  4881.8 1178.57  4896.1 1177.08
  4931.3 1176.08  4953.6 1174.82  4960.0 1174.98  4980.9 1173.85  4986.8 1172.81
  4987.0 1172.31  4990.5 1172.31  4990.8 1172.81  4995.2 1173.77  5009.6 1175.18
  5023.9 1177.44  5052.7 1178.22  5098.1 1180.39  5123.2 1182.24  5152.8 1183.58
  5188.5 1185.96  5224.2 1187.51  5239.0 1189.17  5245.2 1188.96  5259.9 1189.70
#Mann=3,-1,0
  4682.9    0.05       0  4986.8    0.03       0  4990.8    0.05       0
Bank Sta=4986.8,4990.8
Exp/Cntr=0.3,0.1

Type RM Length L Ch R = 1,28062,140,140,140
BEGIN DESCRIPTION:
Mapping XS e5cf9297
END DESCRIPTION:
XS GIS Cut Line= 2
      2856096.12     10185305.45      2855596.32     10184848.05
#Sta/Elev= 30
  4618.4 1193.86  4634.3 1193.86  4641.7 1193.16  4648.5 1193.34  4670.1 1192.38
  4691.0 1190.96  4698.4 1189.91  4719.4 1188.99  4754.5 1186.52  4761.9 1185.46
  4818.7 1180.93  4825.5 1179.96  4832.9 1180.27  4839.6 1179.45  4861.2 1178.68
  4868.0 1177.91  4979.5 1171.99  4979.7 1171.49  4983.2 1171.49  4983.5 1171.99
  4995.7 1172.02  5009.8 1173.04  5045.0 1173.91  5094.3 1176.11  5151.1 1180.47
  5179.4 1183.55  5201.0 1185.22  5222.0 1186.31  5271.3 1189.94  5295.9 1190.18
#Mann=3,-1,0
  4618.4    0.05       0  4979.5    0.03       0  4983.5    0.05       0
Bank Sta=4979.5,4983.5
Exp/Cntr=0.3,0.1

Type RM Length L Ch R = 1,27922,302,302,302
BEGIN DESCRIPTION:
Mapping XS eed7d74f
END DESCRIPTION:
XS GIS Cut Line= 2
      2856153.68     10185178.24      2855726.60     10184784.48
#Sta/Elev= 30
  4637.0 1202.10  4639.1 1202.62  4646.5 1201.40  4653.3 1202.07  4660.7 1200.77
  4688.7 1197.86  4695.8 1196.23  4702.6 1196.52  4710.0 1194.40  4716.8 1194.00
  4738.4 1189.69  4752.5 1188.38  4780.9 1184.36  4844.4 1178.17  4893.7 1174.29
  4972.0 1172.17  4991.0 1171.18  4991.2 1170.68  4994.7 1170.68  4995.0 1171.18
  5000.4 1171.60  5021.3 1171.25  5049.7 1172.61  5056.5 1172.33  5070.7 1173.38
  5078.0 1174.86  5099.0 1175.79  5106.4 1176.78  5148.9 1179.88  5217.9 1183.70
#Mann=3,-1,0
  4637.0    0.05       0  4991.0    0.05       0  4995.0    0.05       0
Bank Sta=4991,4995
Exp/Cntr=0.3,0.1

Type RM Length L Ch R = 1,27620,331,331,331
BEGIN DESCRIPTION:
COTTONWOOD CREEK 01 60.0
END DESCRIPTION:
XS GIS Cut Line= 3
      2856255.70     10185053.14      2855979.93     10184684.03
      2855835.58     10184648.13
#Sta/Elev= 30
  4649.1 1204.38  4671.0 1202.77  4677.3 1201.43  4685.6 1200.72  4712.7 1194.49
  4735.6 1190.48  4756.5 1186.04  4783.1 1181.72  4806.5 1177.27  4821.1 1175.69
  4841.9 1174.85  4856.5 1173.13  4862.8 1173.26  4885.7 1170.89  4935.8 1168.39
  4971.2 1167.28  4985.8 1166.16  4990.0 1165.49  4990.3 1164.99  4993.8 1164.99
  4994.0 1165.49  5006.6 1167.56  5042.1 1170.44  5048.6 1171.35  5092.1 1173.25
  5098.5 1174.10  5178.5 1174.73  5214.7 1175.87  5219.8 1175.42  5258.6 1177.35
#Mann=4,-1,0
  4649.1    0.12       0  4783.1    0.05       0  4990.0    0.03       0
  4994.0    0.05       0
Bank Sta=4990,4994
Exp/Cntr=0.3,0.1

Type RM Length L Ch R = 1,27289,231,231,231
BEGIN DESCRIPTION:
COTTONWOOD CREEK 01 59.0
END DESCRIPTION:
XS GIS Cut Line= 3
      2856502.68     10184903.24      2856294.62     10184712.20
      2856105.71     10184603.13
#Sta/Elev= 30
  4759.7 1187.33  4764.8 1188.18  4771.6 1187.35  4783.0 1187.91  4793.2 1188.00
  4800.0 1187.12  4807.4 1187.49  4814.2 1186.14  4835.7 1185.39  4842.5 1183.93
  4864.1 1182.34  4870.9 1180.58  4885.1 1180.35  4913.4 1175.14  4920.2 1173.37
  4927.6 1172.72  4969.9 1163.01  4977.0 1162.57  4984.3 1160.66  5003.3 1160.33
  5003.6 1159.83  5007.1 1159.83  5007.3 1160.33  5048.5 1163.64  5091.6 1165.01
  5128.9 1167.80  5156.4 1168.34  5193.6 1170.82  5209.3 1172.48  5260.3 1174.71
#Mann=5,-1,0
  4759.7    0.05       0  4783.0    0.12       0  4969.9    0.05       0
  5003.3    0.03       0  5007.3    0.05       0
Bank Sta=5003.3,5007.3
Exp/Cntr=0.3,0.1

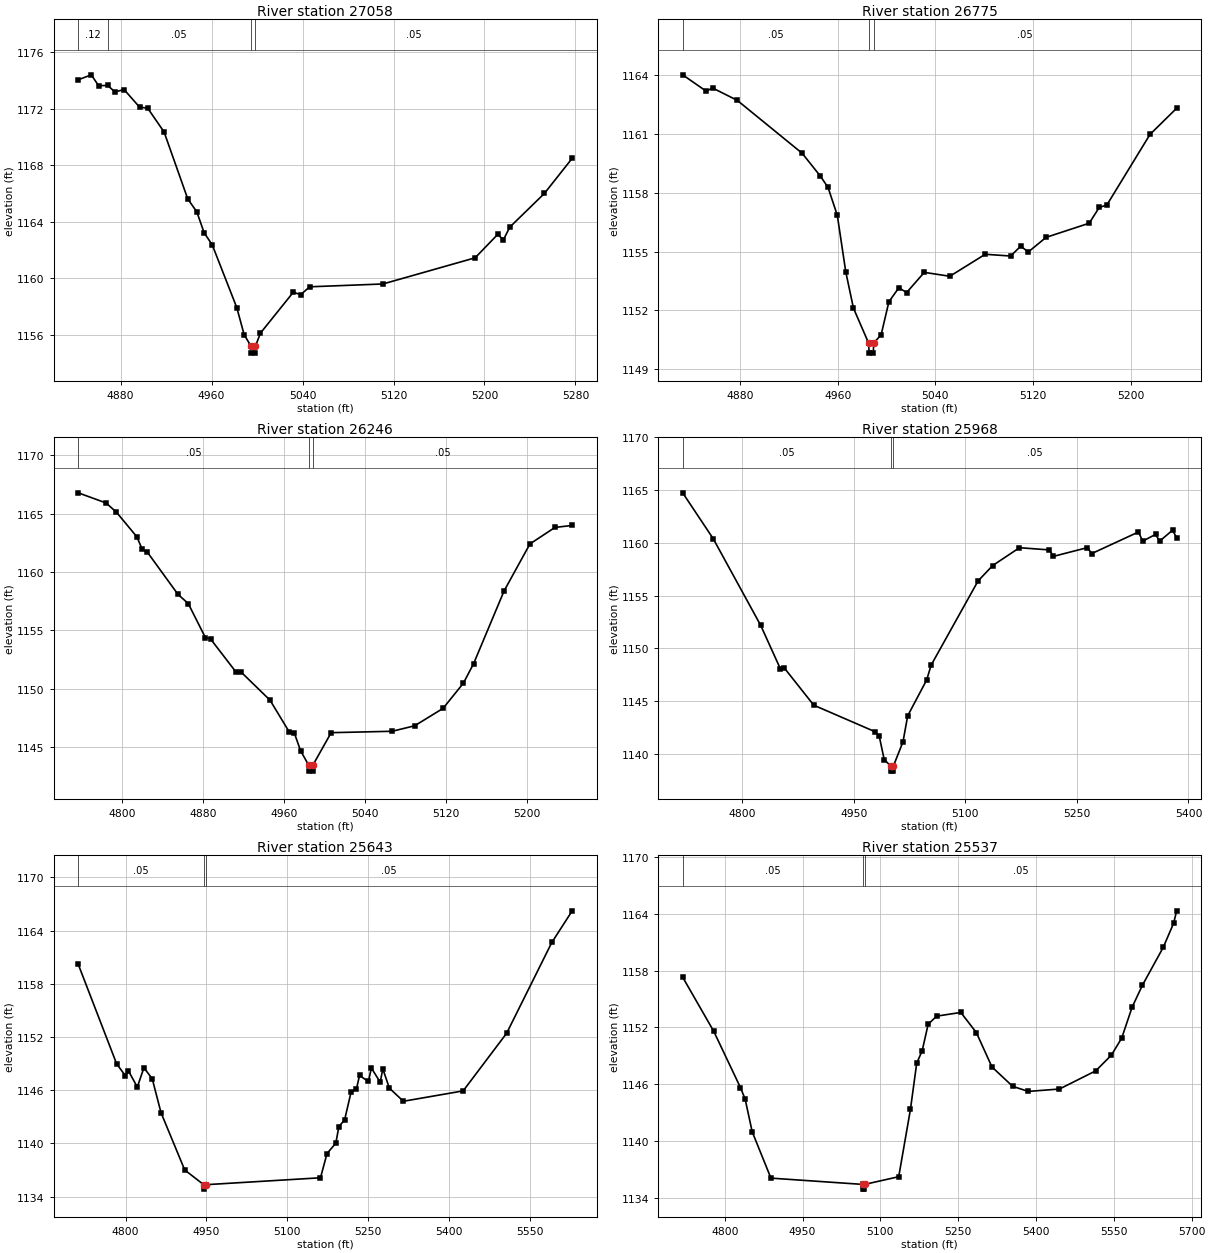
Type RM Length L Ch R = 1,27058,283,283,283
BEGIN DESCRIPTION:
Mapping XS 84efad98
END DESCRIPTION:
XS GIS Cut Line= 3
      2856587.77     10184666.78      2856389.19     10184507.91
      2856211.50     10184477.99
#Sta/Elev= 30
  4842.7 1174.05  4854.2 1174.40  4860.6 1173.63  4868.6 1173.65  4875.0 1173.19
  4883.0 1173.36  4896.6 1172.12  4903.8 1172.04  4918.2 1170.36  4939.0 1165.63
  4947.0 1164.71  4953.4 1163.24  4960.6 1162.37  4982.2 1157.93  4988.6 1156.03
  4994.6 1155.22  4994.9 1154.72  4998.4 1154.72  4998.6 1155.22  5003.0 1156.14
  5031.9 1159.03  5038.3 1158.85  5046.3 1159.41  5110.7 1159.61  5191.8 1161.46
  5211.6 1163.11  5216.7 1162.74  5222.3 1163.63  5252.7 1166.01  5277.2 1168.50
#Mann=4,-1,0
  4842.7    0.12       0  4868.6    0.05       0  4994.6    0.03       0
  4998.6    0.05       0
Bank Sta=4994.6,4998.6
Exp/Cntr=0.3,0.1

Type RM Length L Ch R = 1,26775,529,529,529
BEGIN DESCRIPTION:
COTTONWOOD CREEK 01 58.0
END DESCRIPTION:
XS GIS Cut Line= 3
      2856627.52     10184485.19      2856591.87     10184385.18
      2856355.67     10184203.10
#Sta/Elev= 30
  4833.1 1163.99  4852.3 1163.16  4857.6 1163.32  4877.8 1162.69  4930.9 1160.00
  4945.8 1158.84  4952.1 1158.26  4959.7 1156.84  4966.6 1153.97  4972.9 1152.12
  4985.4 1150.33  4985.7 1149.83  4989.2 1149.83  4989.4 1150.33  4995.6 1150.77
  5001.9 1152.44  5010.1 1153.16  5016.4 1152.91  5030.9 1153.94  5051.8 1153.74
  5080.8 1154.86  5101.6 1154.77  5109.8 1155.27  5116.1 1154.98  5130.6 1155.72
  5165.9 1156.44  5174.1 1157.24  5180.4 1157.37  5215.7 1160.96  5237.5 1162.29
#Mann=3,-1,0
  4833.1    0.05       0  4985.4    0.05       0  4989.4    0.05       0
Bank Sta=4985.4,4989.4
Exp/Cntr=0.3,0.1

Type RM Length L Ch R = 1,26246,278,278,278
BEGIN DESCRIPTION:
COTTONWOOD CREEK 01 57.0
END DESCRIPTION:
XS GIS Cut Line= 3
      2856882.87     10183948.02      2856727.78     10183923.43
      2856398.71     10183951.64
#Sta/Elev= 30
  4757.0 1166.77  4784.5 1165.90  4794.6 1165.12  4814.9 1163.00  4820.1 1161.93
  4825.2 1161.69  4855.4 1158.08  4865.5 1157.30  4882.4 1154.39  4887.5 1154.27
  4912.6 1151.44  4917.6 1151.44  4946.2 1149.03  4965.1 1146.32  4970.1 1146.24
  4976.3 1144.71  4984.4 1143.46  4984.6 1142.96  4988.1 1142.96  4988.4 1143.46
  5006.5 1146.25  5066.7 1146.37  5088.9 1146.84  5116.9 1148.33  5136.9 1150.48
  5147.0 1152.15  5177.1 1158.38  5202.6 1162.40  5227.3 1163.81  5244.3 1163.98
#Mann=3,-1,0
  4757.0    0.05       0  4984.4    0.03       0  4988.4    0.05       0
Bank Sta=4984.4,4988.4
Exp/Cntr=0.3,0.1

Type RM Length L Ch R = 1,25968,325,325,325
BEGIN DESCRIPTION:
COTTONWOOD CREEK 01 56.0
END DESCRIPTION:
XS GIS Cut Line= 3
      2856773.20     10183626.45      2856373.33     10183757.06
      2856270.50     10183977.71
#Sta/Elev= 30
  4720.0 1164.75  4761.1 1160.40  4824.9 1152.19  4851.5 1148.05  4856.8 1148.14
  4896.2 1144.63  4979.1 1142.10  4984.3 1141.68  4990.9 1139.48  4999.4 1138.88
  4999.7 1138.38  5003.2 1138.38  5003.4 1138.88  5016.2 1141.16  5022.5 1143.62
  5048.1 1147.03  5054.0 1148.42  5117.1 1156.40  5136.8 1157.86  5172.8 1159.55
  5213.0 1159.34  5218.5 1158.73  5264.2 1159.56  5269.8 1158.99  5332.8 1161.04
  5338.4 1160.17  5355.7 1160.81  5361.2 1160.17  5378.6 1161.21  5384.1 1160.49
#Mann=3,-1,0
  4720.0    0.05       0  4999.4    0.03       0  5003.4    0.05       0
Bank Sta=4999.4,5003.4
Exp/Cntr=0.3,0.1

Type RM Length L Ch R = 1,25643,106,106,106
BEGIN DESCRIPTION:
Mapping XS ec6e39da
END DESCRIPTION:
XS GIS Cut Line= 3
      2856733.43     10183571.59      2856232.20     10183306.79
      2855885.00     10183353.42
#Sta/Elev= 30
  4712.0 1160.21  4783.3 1148.98  4799.7 1147.63  4805.3 1148.18  4821.7 1146.36
  4833.9 1148.54  4849.4 1147.30  4865.7 1143.47  4909.7 1137.01  4945.0 1135.35
  4945.2 1134.85  4949.0 1135.35  5161.8 1136.13  5173.9 1138.86  5190.3 1140.04
  5195.9 1141.90  5206.6 1142.66  5218.4 1145.75  5228.6 1146.16  5234.3 1147.67
  5250.7 1146.99  5256.3 1148.51  5272.7 1146.91  5277.5 1148.42  5289.7 1146.24
  5315.7 1144.76  5426.7 1145.93  5507.4 1152.43  5591.3 1162.67  5629.2 1166.24
#Mann=3,-1,0
  4712.0    0.05       0  4945.0    0.05       0  4949.0    0.05       0
Bank Sta=4945,4949
Exp/Cntr=0.3,0.1

Type RM Length L Ch R = 1,25537,101,101,101
BEGIN DESCRIPTION:
Mapping XS b173ef0a
END DESCRIPTION:
XS GIS Cut Line= 3
      2856754.30     10183465.70      2856311.64     10183233.02
      2855859.84     10183218.89
#Sta/Elev= 30
  4719.0 1157.30  4778.9 1151.59  4830.4 1145.65  4839.4 1144.44  4853.0 1140.99
  4889.1 1136.10  5065.7 1135.44  5065.9 1134.94  5069.4 1134.94  5069.7 1135.44
  5135.4 1136.25  5158.0 1143.35  5170.1 1148.23  5180.6 1149.53  5192.1 1152.33
  5208.5 1153.19  5255.1 1153.58  5285.1 1151.45  5315.1 1147.83  5355.1 1145.78
  5385.1 1145.25  5445.2 1145.50  5515.2 1147.42  5545.2 1149.07  5565.2 1150.87
  5585.2 1154.13  5605.2 1156.46  5645.2 1160.44  5665.3 1163.00  5671.1 1164.30
#Mann=3,-1,0
  4719.0    0.05       0  5065.7    0.05       0  5069.7    0.05       0
Bank Sta=5065.7,5069.7
Exp/Cntr=0.3,0.1

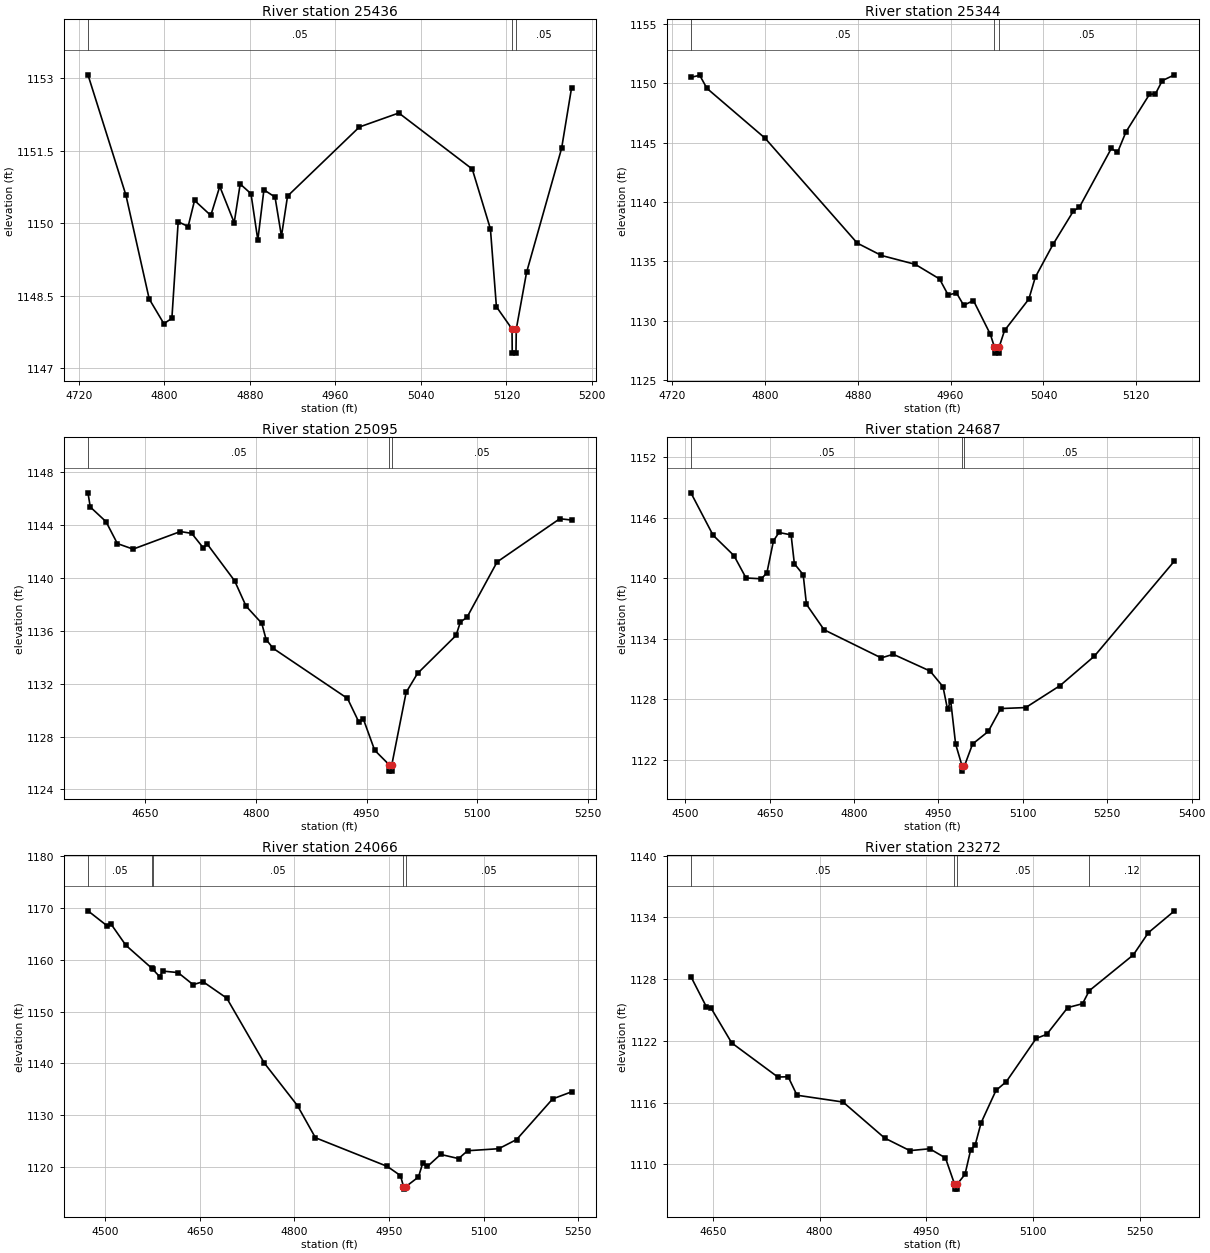
Type RM Length L Ch R = 1,25436,92,92,92
BEGIN DESCRIPTION:
Mapping XS ea2dfcc2
END DESCRIPTION:
XS GIS Cut Line= 4
      2856765.60     10183371.09      2856661.58     10183304.90
      2856512.14     10183227.34      2856367.26     10183157.72
#Sta/Elev= 30
  4728.5 1153.07  4764.0 1150.58  4785.8 1148.43  4799.5 1147.92  4807.0 1148.03
  4812.9 1150.03  4822.2 1149.93  4828.2 1150.47  4843.4 1150.16  4851.8 1150.76
  4865.3 1150.01  4870.9 1150.81  4881.0 1150.61  4887.4 1149.65  4893.1 1150.69
  4903.5 1150.54  4909.5 1149.73  4915.2 1150.56  4982.4 1151.99  5019.3 1152.28
  5088.0 1151.12  5105.0 1149.88  5110.6 1148.27  5125.2 1147.81  5125.4 1147.31
  5128.9 1147.31  5129.2 1147.81  5138.8 1148.98  5171.6 1151.55  5180.9 1152.80
#Mann=3,-1,0
  4728.5    0.05       0  5125.2    0.05       0  5129.2    0.05       0
Bank Sta=5125.2,5129.2
Exp/Cntr=0.3,0.1

Type RM Length L Ch R = 1,25344,249,249,249
BEGIN DESCRIPTION:
COTTONWOOD CREEK 01 55.0
END DESCRIPTION:
XS GIS Cut Line= 3
      2856763.74     10183304.91      2856551.88     10183147.90
      2856405.69     10183103.11
#Sta/Elev= 30
  4736.3 1150.50  4743.9 1150.67  4750.1 1149.57  4800.2 1145.37  4879.6 1136.53
  4900.4 1135.49  4929.6 1134.74  4950.5 1133.51  4957.9 1132.16  4965.1 1132.33
  4971.3 1131.29  4979.7 1131.69  4994.3 1128.84  4997.8 1127.76  4998.1 1127.26
  5001.6 1127.26  5001.8 1127.76  5006.5 1129.17  5027.4 1131.81  5033.0 1133.66
  5048.3 1136.43  5065.8 1139.23  5071.0 1139.56  5098.5 1144.51  5103.8 1144.17
  5111.1 1145.90  5131.3 1149.06  5136.5 1149.11  5142.4 1150.22  5152.9 1150.71
#Mann=3,-1,0
  4736.3    0.05       0  4997.8    0.05       0  5001.8    0.05       0
Bank Sta=4997.8,5001.8
Exp/Cntr=0.3,0.1

Type RM Length L Ch R = 1,25095,408,408,408
BEGIN DESCRIPTION:
COTTONWOOD CREEK 01 54.0
END DESCRIPTION:
XS GIS Cut Line= 3
      2856943.40     10183338.92      2856678.60     10182905.78
      2856574.56     10182801.75
#Sta/Elev= 30
  4572.8 1146.45  4575.9 1145.38  4597.2 1144.27  4612.6 1142.61  4633.9 1142.19
  4697.9 1143.52  4713.3 1143.38  4728.7 1142.30  4734.6 1142.55  4771.4 1139.79
  4786.8 1137.88  4808.1 1136.58  4814.0 1135.35  4823.6 1134.68  4924.2 1130.89
  4939.7 1129.09  4945.5 1129.36  4961.0 1126.97  4980.3 1125.89  4980.5 1125.39
  4984.0 1125.39  4984.3 1125.89  5003.6 1131.35  5019.0 1132.78  5071.2 1135.66
  5077.1 1136.68  5085.9 1137.02  5126.8 1141.22  5211.7 1144.49  5227.6 1144.39
#Mann=3,-1,0
  4572.8    0.05       0  4980.3    0.05       0  4984.3    0.05       0
Bank Sta=4980.3,4984.3
Exp/Cntr=0.3,0.1

Type RM Length L Ch R = 1,24687,621,621,621
BEGIN DESCRIPTION:
COTTONWOOD CREEK 01 53.0
END DESCRIPTION:
XS GIS Cut Line= 3
      2857281.99     10183359.74      2857058.80     10182979.55
      2856868.52     10182606.54
#Sta/Elev= 30
  4509.9 1148.46  4549.3 1144.26  4586.4 1142.24  4607.9 1140.02  4635.2 1139.94
  4645.0 1140.54  4656.7 1143.71  4666.5 1144.53  4688.0 1144.29  4693.8 1141.43
  4709.5 1140.35  4715.3 1137.41  4746.6 1134.89  4848.2 1132.10  4869.6 1132.46
  4935.0 1130.80  4958.0 1129.25  4966.1 1126.99  4971.7 1127.85  4980.4 1123.57
  4992.0 1121.38  4992.2 1120.88  4996.0 1121.38  5010.6 1123.57  5038.4 1124.81
  5060.6 1127.08  5105.1 1127.18  5166.2 1129.36  5227.2 1132.28  5369.5 1141.71
#Mann=3,-1,0
  4509.9    0.05       0  4992.0    0.05       0  4996.0    0.05       0
Bank Sta=4992,4996
Exp/Cntr=0.3,0.1

Type RM Length L Ch R = 1,24066,794,794,794
BEGIN DESCRIPTION:
COTTONWOOD CREEK 01 52.0
END DESCRIPTION:
XS GIS Cut Line= 3
      2857904.29     10182871.72      2857628.15     10182758.24
      2857276.29     10182449.89
#Sta/Elev= 30
  4472.8 1169.50  4503.5 1166.57  4508.9 1167.02  4532.8 1162.85  4574.2 1158.38
  4575.2 1158.25  4586.2 1156.79  4591.6 1157.85  4615.5 1157.57  4639.5 1155.23
  4655.1 1155.81  4692.8 1152.62  4752.4 1140.06  4804.9 1131.84  4833.3 1125.65
  4947.2 1120.11  4968.1 1118.33  4972.8 1116.22  4973.0 1115.72  4976.8 1116.22
  4996.6 1118.07  5003.2 1120.70  5010.8 1120.10  5031.7 1122.43  5060.2 1121.62
  5074.4 1123.14  5123.8 1123.53  5152.2 1125.31  5209.2 1133.15  5239.2 1134.52
#Mann=5,-1,0
  4472.8    0.05       0  4574.2    0.12       0  4575.2    0.05       0
  4972.8    0.05       0  4976.8    0.05       0
Bank Sta=4972.8,4976.8
Exp/Cntr=0.3,0.1

Type RM Length L Ch R = 1,23272,357,357,357
BEGIN DESCRIPTION:
COTTONWOOD CREEK 01 51.0
END DESCRIPTION:
XS GIS Cut Line= 3
      2857805.69     10182253.11      2857457.91     10181995.95
      2857255.70     10181853.12
#Sta/Elev= 30
  4619.1 1128.24  4641.0 1125.29  4647.3 1125.20  4676.5 1121.80  4741.3 1118.49
  4755.9 1118.51  4768.3 1116.72  4833.0 1116.06  4891.6 1112.56  4927.0 1111.34
  4954.9 1111.52  4977.1 1110.63  4989.8 1108.10  4990.0 1107.60  4993.5 1107.60
  4993.8 1108.10  5004.6 1109.04  5012.6 1111.43  5018.8 1111.87  5027.2 1114.04
  5048.1 1117.18  5062.8 1118.05  5104.7 1122.24  5119.5 1122.63  5149.0 1125.23
  5169.9 1125.61  5179.3 1126.87  5241.3 1130.35  5262.5 1132.51  5299.2 1134.63
#Mann=4,-1,0
  4619.1    0.05       0  4989.8    0.03       0  4993.8    0.05       0
  5179.3    0.12       0
Bank Sta=4989.8,4993.8
Exp/Cntr=0.3,0.1

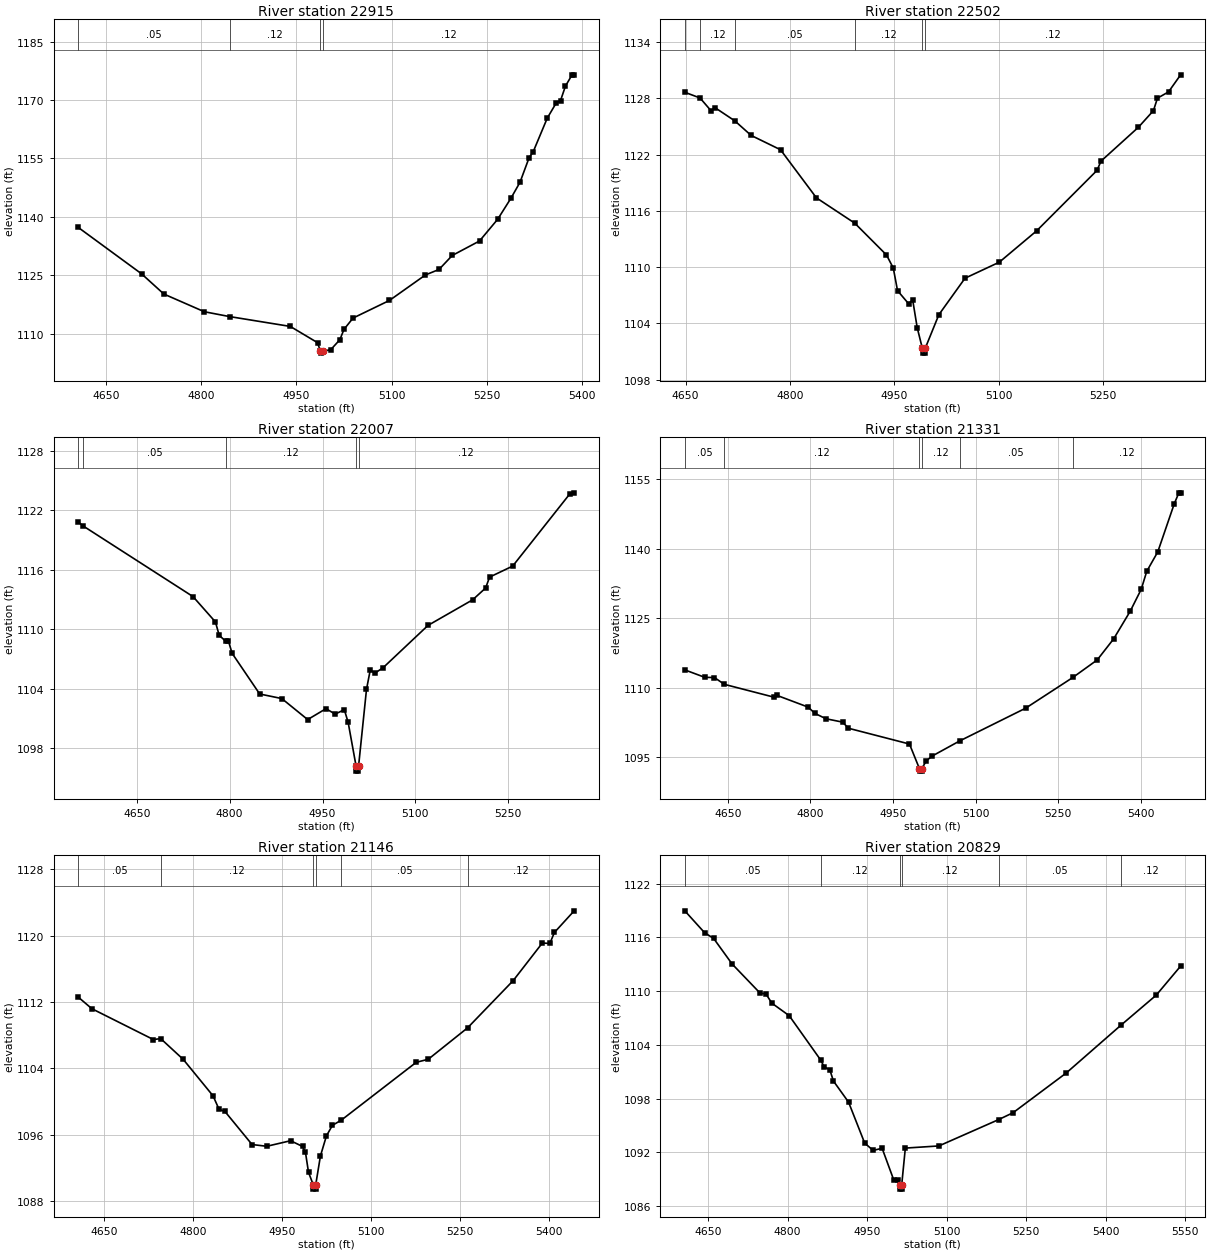
Type RM Length L Ch R = 1,22915,413,413,413
BEGIN DESCRIPTION:
COTTONWOOD CREEK 01 50.0
END DESCRIPTION:
XS GIS Cut Line= 3
      2857955.70     10182103.13      2857703.75     10181801.00
      2857455.65     10181503.07
#Sta/Elev= 30
  4606.6 1137.24  4706.2 1125.34  4741.3 1120.15  4805.1 1115.60  4845.1 1114.35
  4940.5 1111.83  4983.4 1107.66  4988.0 1105.47  4988.2 1104.97  4992.0 1105.47
  5004.3 1105.87  5018.6 1108.41  5025.1 1111.08  5039.4 1113.98  5096.7 1118.50
  5153.4 1125.05  5174.8 1126.46  5195.6 1130.05  5238.6 1133.77  5267.2 1139.35
  5288.1 1144.75  5302.4 1148.86  5316.7 1155.15  5323.2 1156.70  5345.3 1165.32
  5359.7 1169.30  5366.2 1169.82  5374.0 1173.56  5384.4 1176.45  5387.7 1176.45
#Mann=4,-1,0
  4606.6    0.05       0  4845.1    0.12       0  4988.0    0.07       0
  4992.0    0.12       0
Bank Sta=4988,4992
Exp/Cntr=0.3,0.1

Type RM Length L Ch R = 1,22502,495,495,495
BEGIN DESCRIPTION:
COTTONWOOD CREEK 01 49.0
END DESCRIPTION:
XS GIS Cut Line= 3
      2858212.61     10181937.28      2858076.45     10181723.57
      2857852.39     10181322.63
#Sta/Elev= 30
  4648.8 1128.66  4670.7 1128.05  4686.5 1126.69  4692.4 1127.01  4720.7 1125.61
  4744.1 1124.06  4786.4 1122.53  4838.0 1117.40  4893.1 1114.70  4938.7 1111.31
  4948.5 1109.91  4954.6 1107.50  4970.6 1106.10  4976.3 1106.54  4982.9 1103.54
  4990.3 1101.34  4990.6 1100.84  4994.1 1100.84  4994.3 1101.34  5014.0 1104.94
  5051.6 1108.83  5100.9 1110.54  5154.5 1113.88  5241.3 1120.33  5247.1 1121.32
  5300.7 1124.92  5322.4 1126.70  5328.2 1128.03  5344.1 1128.70  5361.5 1130.52
#Mann=6,-1,0
  4648.8    0.05       0  4670.7    0.12       0  4720.7    0.05       0
  4893.1    0.12       0  4990.3    0.07       0  4994.3    0.12       0
Bank Sta=4990.3,4994.3
Exp/Cntr=0.3,0.1

Type RM Length L Ch R = 1,22007,676,676,676
BEGIN DESCRIPTION:
COTTONWOOD CREEK 01 48.0
END DESCRIPTION:
XS GIS Cut Line= 3
      2858621.23     10181704.68      2858316.67     10181271.49
      2858155.71     10181053.15
#Sta/Elev= 30
  4555.6 1120.79  4563.8 1120.38  4740.9 1113.27  4777.0 1110.72  4783.1 1109.37
  4793.6 1108.77  4797.9 1108.81  4804.0 1107.55  4848.5 1103.45  4884.2 1102.99
  4926.0 1100.87  4955.6 1101.97  4970.4 1101.42  4985.2 1101.87  4991.4 1100.58
  5004.2 1096.17  5004.4 1095.67  5007.9 1095.67  5008.2 1096.17  5021.0 1103.91
  5027.1 1105.88  5034.3 1105.54  5048.0 1106.11  5120.4 1110.37  5192.5 1112.95
  5213.4 1114.14  5219.8 1115.24  5257.1 1116.35  5349.1 1123.61  5356.4 1123.74
#Mann=5,-1,0
  4555.6    0.12       0  4563.8    0.05       0  4793.6    0.12       0
  5004.2    0.07       0  5008.2    0.12       0
Bank Sta=5004.2,5008.2
Exp/Cntr=0.3,0.1

Type RM Length L Ch R = 1,21331,185,185,185
BEGIN DESCRIPTION:
COTTONWOOD CREEK 01 47.0
END DESCRIPTION:
XS GIS Cut Line= 3
      2858685.52     10181536.33      2858761.18     10181052.08
      2858755.51     10180641.64
#Sta/Elev= 30
  4571.9 1113.82  4608.0 1112.22  4625.8 1112.16  4643.7 1110.70  4733.5 1107.94
  4738.5 1108.35  4796.2 1105.77  4807.9 1104.45  4828.2 1103.27  4858.6 1102.54
  4869.1 1101.22  4980.0 1097.81  4998.2 1092.46  4998.5 1091.96  5002.0 1091.96
  5002.2 1092.46  5010.4 1094.15  5020.5 1095.17  5071.2 1098.48  5191.0 1105.55
  5276.7 1112.18  5321.0 1115.97  5351.0 1120.54  5381.0 1126.50  5401.0 1131.24
  5411.0 1135.11  5431.0 1139.30  5461.0 1149.71  5469.3 1152.05  5472.5 1152.05
#Mann=6,-1,0
  4571.9    0.05       0  4643.7    0.12       0  4998.2    0.07       0
  5002.2    0.12       0  5071.2    0.05       0  5276.7    0.12       0
Bank Sta=4998.2,5002.2
Exp/Cntr=0.3,0.1

Type RM Length L Ch R = 1,21146,317,317,317
BEGIN DESCRIPTION:
COTTONWOOD CREEK 01 46.0
END DESCRIPTION:
XS GIS Cut Line= 3
      2858887.91     10181528.78      2858942.77     10181040.73
      2858997.63     10180700.24
#Sta/Elev= 30
  4606.2 1112.59  4629.0 1111.20  4732.7 1107.48  4745.1 1107.59  4783.0 1105.09
  4833.3 1100.69  4843.4 1099.07  4853.4 1098.80  4899.1 1094.81  4923.9 1094.60
  4964.1 1095.27  4984.2 1094.58  4989.2 1093.85  4994.3 1091.46  5002.4 1089.93
  5002.6 1089.43  5006.1 1089.43  5006.4 1089.93  5014.4 1093.43  5024.5 1095.85
  5034.5 1097.12  5049.9 1097.77  5175.9 1104.73  5196.2 1105.10  5262.5 1108.89
  5339.4 1114.59  5388.6 1119.13  5401.2 1119.07  5408.9 1120.40  5442.2 1123.01
#Mann=6,-1,0
  4606.2    0.05       0  4745.1    0.12       0  5002.4    0.07       0
  5006.4    0.12       0  5049.9    0.05       0  5262.5    0.12       0
Bank Sta=5002.4,5006.4
Exp/Cntr=0.3,0.1

Type RM Length L Ch R = 1,20829,381,381,381
BEGIN DESCRIPTION:
Mapping XS f9ab1f30
END DESCRIPTION:
XS GIS Cut Line= 3
      2858995.71     10181702.81      2859181.10     10181288.52
      2859186.77     10180807.13
#Sta/Elev= 30
  4606.2 1118.96  4643.5 1116.52  4660.6 1115.88  4695.4 1113.03  4748.3 1109.77
  4759.2 1109.69  4770.5 1108.65  4803.1 1107.26  4863.1 1102.26  4868.8 1101.55
  4879.8 1101.22  4886.5 1099.97  4915.1 1097.61  4945.5 1093.04  4961.5 1092.22
  4978.4 1092.46  5000.3 1088.93  5007.9 1088.94  5011.4 1088.40  5011.6 1087.90
  5015.1 1087.90  5015.4 1088.40  5022.2 1092.48  5085.5 1092.72  5198.2 1095.66
  5225.5 1096.43  5325.5 1100.85  5429.6 1106.23  5495.5 1109.55  5541.5 1112.79
#Mann=6,-1,0
  4606.2    0.05       0  4863.1    0.12       0  5011.4    0.07       0
  5015.4    0.12       0  5198.2    0.05       0  5429.6    0.12       0
Bank Sta=5011.4,5015.4
Exp/Cntr=0.3,0.1

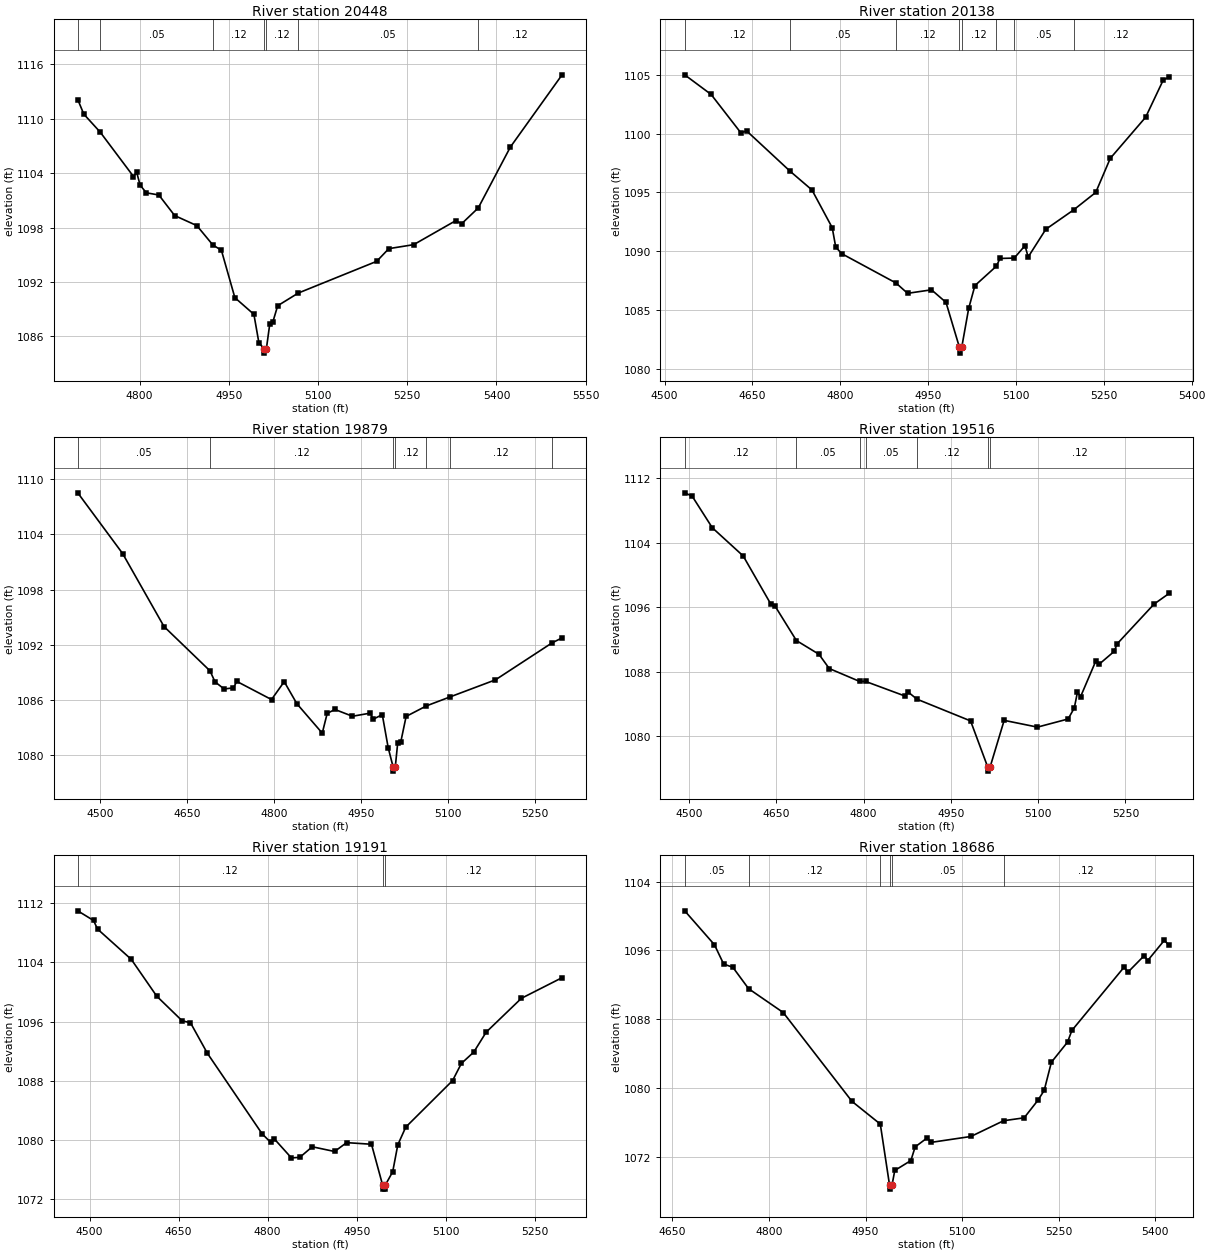
Type RM Length L Ch R = 1,20448,310,310,310
BEGIN DESCRIPTION:
COTTONWOOD CREEK 01 45.0
END DESCRIPTION:
XS GIS Cut Line= 3
      2859531.04     10181562.79      2859394.85     10181142.87
      2859319.22     10180777.98
#Sta/Elev= 30
  4696.2 1112.12  4706.4 1110.51  4733.9 1108.53  4789.9 1103.63  4795.2 1104.11
  4801.0 1102.68  4811.5 1101.83  4832.5 1101.59  4859.1 1099.32  4896.4 1098.21
  4923.1 1096.09  4937.7 1095.48  4960.3 1090.26  4992.3 1088.42  5000.7 1085.28
  5009.3 1084.64  5009.5 1084.14  5013.3 1084.64  5019.0 1087.37  5024.3 1087.62
  5032.3 1089.37  5066.9 1090.77  5198.7 1094.27  5219.1 1095.67  5260.9 1096.11
  5331.4 1098.75  5341.7 1098.43  5369.4 1100.16  5423.4 1106.88  5510.3 1114.85
#Mann=7,-1,0
  4696.2    0.12       0  4733.9    0.05       0  4923.1    0.12       0
  5009.3    0.07       0  5013.3    0.12       0  5066.9    0.05       0
  5369.4    0.12       0
Bank Sta=5009.3,5013.3
Exp/Cntr=0.3,0.1

Type RM Length L Ch R = 1,20138,259,259,259
BEGIN DESCRIPTION:
COTTONWOOD CREEK 01 44.0
END DESCRIPTION:
XS GIS Cut Line= 3
      2859640.74     10181547.68      2859705.06     10181148.54
      2859555.68     10180753.10
#Sta/Elev= 30
  4534.3 1105.01  4579.4 1103.34  4630.1 1100.08  4640.2 1100.23  4714.6 1096.79
  4751.6 1095.21  4786.2 1092.00  4792.2 1090.35  4802.3 1089.79  4895.1 1087.29
  4914.9 1086.41  4955.7 1086.71  4980.5 1085.64  5003.4 1081.82  5003.6 1081.32
  5007.4 1081.82  5019.2 1085.12  5029.9 1087.07  5066.5 1088.72  5072.7 1089.38
  5097.0 1089.41  5115.4 1090.47  5120.8 1089.50  5150.9 1091.86  5198.4 1093.51
  5236.2 1095.00  5261.0 1097.90  5321.4 1101.40  5351.5 1104.57  5361.3 1104.82
#Mann=8,-1,0
  4534.3    0.12       0  4714.6    0.05       0  4895.1    0.12       0
  5003.4    0.07       0  5007.4    0.12       0  5066.5    0.12       0
  5097.0    0.05       0  5198.4    0.12       0
Bank Sta=5003.4,5007.4
Exp/Cntr=0.3,0.1

Type RM Length L Ch R = 1,19879,363,363,363
BEGIN DESCRIPTION:
Mapping XS 1b521545
END DESCRIPTION:
XS GIS Cut Line= 3
      2860170.36     10181521.14      2859952.85     10181120.17
      2859865.85     10180751.36
#Sta/Elev= 30
  4461.7 1108.54  4539.1 1101.92  4610.4 1093.97  4689.7 1089.14  4698.4 1087.94
  4714.1 1087.16  4730.2 1087.29  4735.9 1087.99  4795.8 1086.01  4817.7 1087.96
  4839.6 1085.55  4883.3 1082.35  4891.8 1084.50  4905.1 1084.93  4935.4 1084.19
  4966.0 1084.53  4971.1 1083.86  4986.8 1084.37  4997.0 1080.76  5005.3 1078.71
  5005.6 1078.21  5009.3 1078.71  5013.4 1081.29  5018.6 1081.36  5027.9 1084.17
  5062.9 1085.32  5102.9 1086.28  5182.0 1088.16  5279.6 1092.19  5296.8 1092.73
#Mann=7,-1,0
  4461.7    0.05       0  4689.7    0.12       0  5005.3    0.07       0
  5009.3    0.12       0  5062.9    0.05       0  5102.9    0.12       0
  5279.6    0.05       0
Bank Sta=5005.3,5009.3
Exp/Cntr=0.3,0.1

Type RM Length L Ch R = 1,19516,325,325,325
BEGIN DESCRIPTION:
COTTONWOOD CREEK 01 43.0
END DESCRIPTION:
XS GIS Cut Line= 3
      2860467.36     10181405.81      2860289.54     10180982.09
      2860170.53     10180628.82
#Sta/Elev= 30
  4492.5 1110.17  4505.3 1109.76  4539.9 1105.84  4593.0 1102.34  4640.4 1096.38
  4647.3 1096.17  4684.5 1091.84  4723.2 1090.14  4740.9 1088.37  4793.1 1086.77
  4803.3 1086.77  4870.6 1084.97  4876.0 1085.48  4891.6 1084.57  4983.8 1081.87
  5013.3 1076.14  5013.6 1075.64  5017.3 1076.14  5041.5 1081.94  5098.7 1081.10
  5151.4 1082.11  5162.0 1083.47  5167.5 1085.44  5172.8 1084.87  5199.0 1089.30
  5204.2 1088.87  5230.5 1090.49  5235.9 1091.45  5299.2 1096.37  5324.8 1097.68
#Mann=7,-1,0
  4492.5    0.12       0  4684.5    0.05       0  4793.1    0.12       0
  4803.3    0.05       0  4891.6    0.12       0  5013.3    0.07       0
  5017.3    0.12       0
Bank Sta=5013.3,5017.3
Exp/Cntr=0.3,0.1

Type RM Length L Ch R = 1,19191,505,505,505
BEGIN DESCRIPTION:
COTTONWOOD CREEK 01 42.0
END DESCRIPTION:
XS GIS Cut Line= 3
      2860798.35     10181088.00      2860516.53     10180764.56
      2860200.62     10180541.35
#Sta/Elev= 30
  4480.1 1111.00  4506.7 1109.69  4513.4 1108.53  4570.3 1104.42  4613.1 1099.44
  4655.8 1096.11  4670.0 1095.83  4698.5 1091.69  4790.6 1080.79  4804.9 1079.64
  4811.5 1080.07  4840.0 1077.52  4854.2 1077.60  4875.1 1079.03  4912.7 1078.39
  4933.0 1079.59  4974.9 1079.37  4993.8 1073.79  4994.1 1073.29  4997.6 1073.29
  4997.8 1073.79  5010.6 1075.64  5019.2 1079.29  5032.6 1081.69  5111.5 1088.00
  5126.3 1090.32  5147.2 1091.86  5168.1 1094.56  5227.3 1099.14  5295.9 1101.94
#Mann=3,-1,0
  4480.1    0.12       0  4993.8    0.07       0  4997.8    0.12       0
Bank Sta=4993.8,4997.8
Exp/Cntr=0.3,0.1

Type RM Length L Ch R = 1,18686,567,567,567
BEGIN DESCRIPTION:
COTTONWOOD CREEK 01 41.0
END DESCRIPTION:
XS GIS Cut Line= 3
      2861029.12     10180724.82      2860855.11     10180512.99
      2860403.04     10180355.99
#Sta/Elev= 30
  4669.0 1100.60  4715.2 1096.66  4729.5 1094.42  4743.9 1094.03  4768.3 1091.55
  4822.1 1088.78  4929.0 1078.45  4973.0 1075.81  4987.3 1068.75  4987.6 1068.25
  4991.3 1068.75  4995.5 1070.42  5020.5 1071.57  5027.2 1073.16  5046.3 1074.23
  5051.6 1073.68  5113.8 1074.37  5164.6 1076.20  5196.6 1076.54  5217.8 1078.56
  5227.7 1079.72  5238.9 1083.00  5264.1 1085.35  5270.7 1086.69  5352.2 1094.08
  5357.5 1093.44  5383.3 1095.40  5388.6 1094.82  5414.4 1097.17  5421.7 1096.60
#Mann=6,-1,0
  4669.0    0.05       0  4768.3    0.12       0  4973.0    0.05       0
  4987.3    0.05       0  4991.3    0.05       0  5164.6    0.12       0
Bank Sta=4987.3,4991.3
Exp/Cntr=0.3,0.1