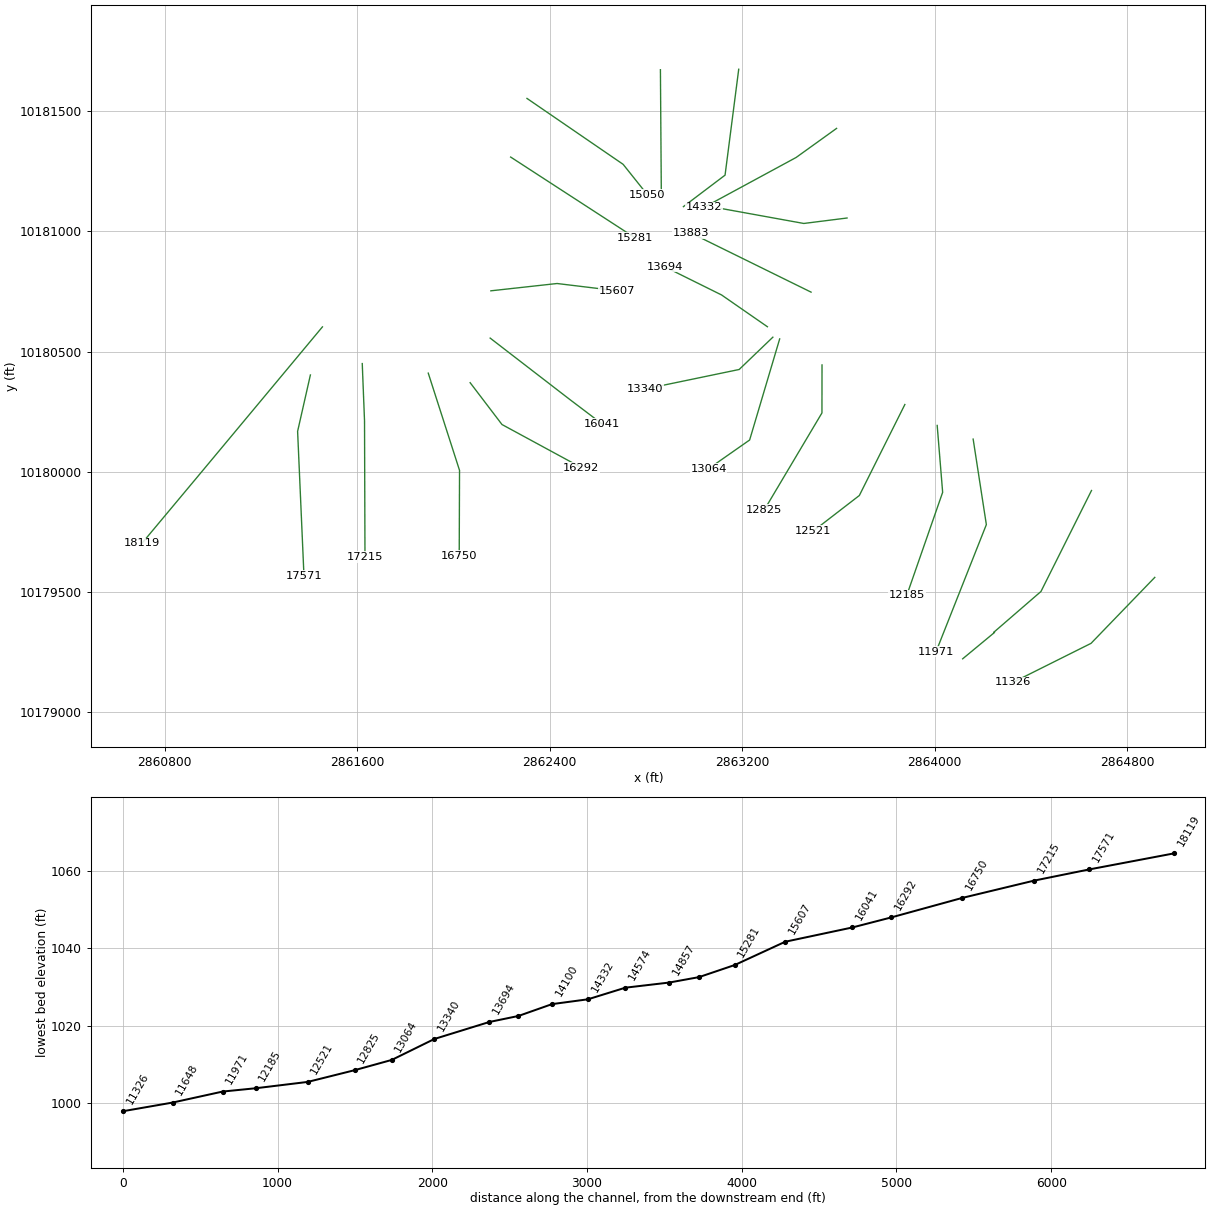
HEC-RAS study COTTONWOOD CREEK 01.prj: COTTONWOOD CREEK 01 Base Level Engineering

--- COTTONWOOD CREEK 01.g01 (geometry) --- (continued)

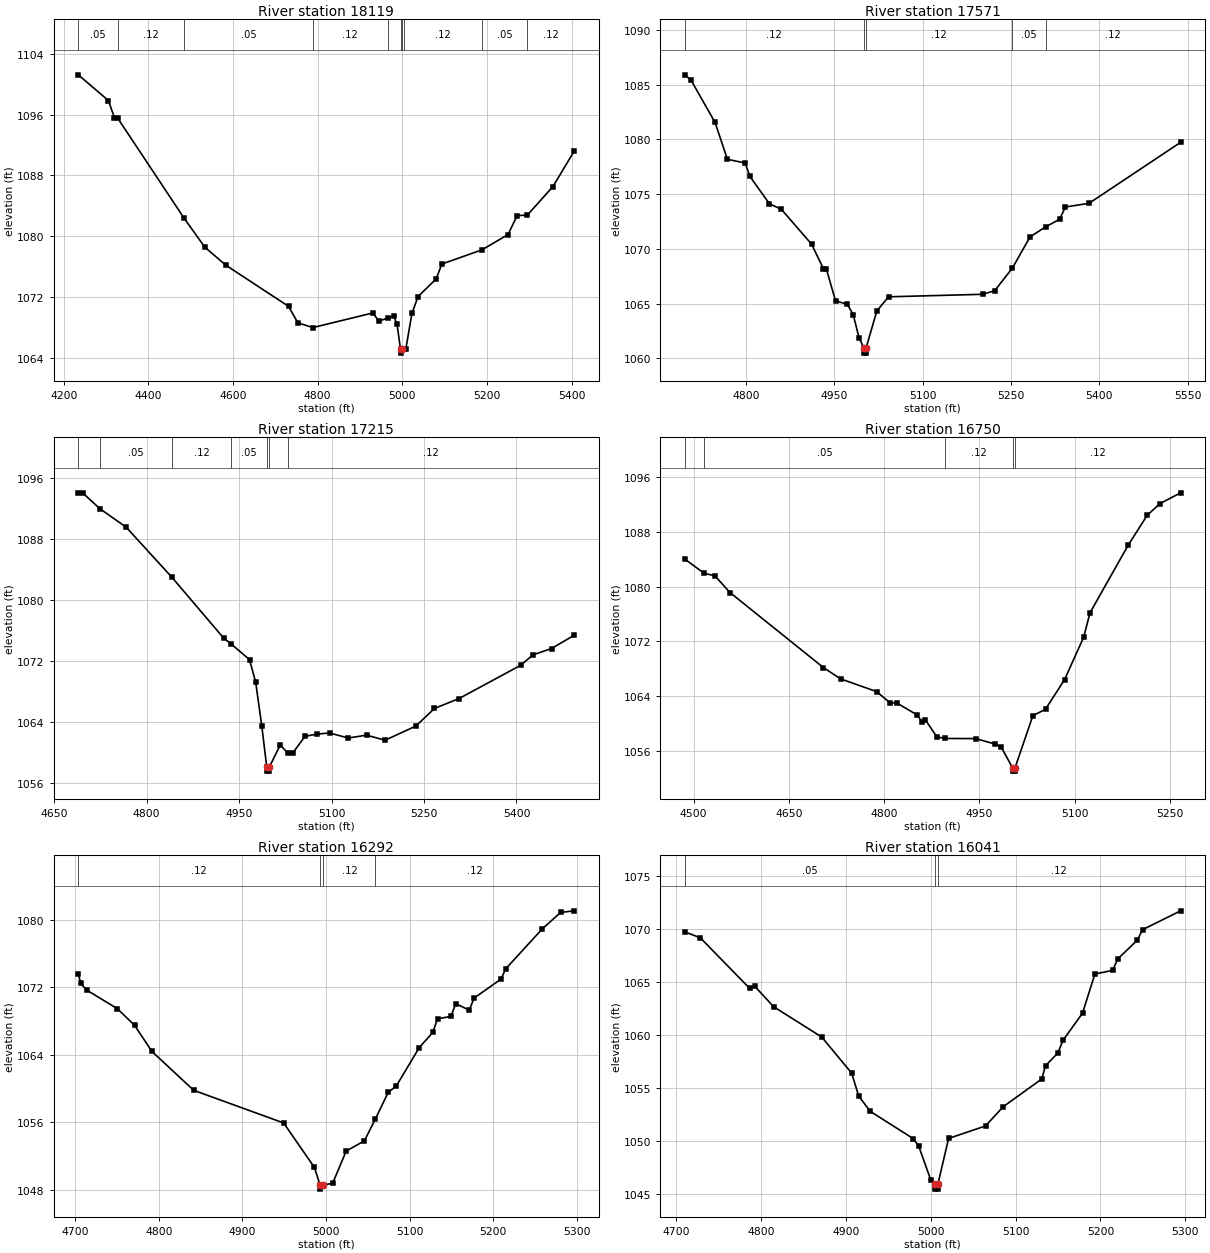
Type RM Length L Ch R = 1,18119,548,548,548
BEGIN DESCRIPTION:
COTTONWOOD CREEK 01 40.0
END DESCRIPTION:
XS GIS Cut Line= 3
      2861455.69     10180603.12      2860966.00     10180015.00
      2860705.72     10179703.15
#Sta/Elev= 30
  4234.7 1101.23  4305.7 1097.85  4320.0 1095.60  4328.1 1095.50  4484.8 1082.37
  4533.5 1078.58  4582.9 1076.22  4731.3 1070.80  4753.5 1068.63  4788.9 1068.01
  4930.5 1069.93  4944.8 1068.86  4965.8 1069.27  4980.0 1069.51  4987.8 1068.42
  4996.0 1065.15  4996.2 1064.65  5000.0 1065.15  5004.7 1065.16  5008.6 1065.23
  5022.9 1069.87  5037.3 1072.08  5080.2 1074.41  5093.6 1076.36  5188.1 1078.22
  5249.9 1080.23  5271.5 1082.73  5295.5 1082.78  5356.1 1086.55  5406.2 1091.19
#Mann=10,-1,0
  4234.7    0.05       0  4328.1    0.12       0  4484.8    0.05       0
  4788.9    0.12       0  4965.8    0.05       0  4996.0    0.05       0
  5000.0    0.05       0  5004.7    0.12       0  5188.1    0.05       0
  5295.5    0.12       0
Bank Sta=4996,5000
Exp/Cntr=0.3,0.1

Type RM Length L Ch R = 1,17571,356,356,356
BEGIN DESCRIPTION:
COTTONWOOD CREEK 01 39.0
END DESCRIPTION:
XS GIS Cut Line= 3
      2861405.69     10180403.15      2861352.59     10180168.73
      2861379.05     10179567.67
#Sta/Elev= 30
  4696.0 1085.89  4706.3 1085.43  4747.3 1081.55  4768.4 1078.18  4798.6 1077.84
  4806.4 1076.63  4839.6 1074.13  4860.1 1073.61  4911.4 1070.43  4931.5 1068.17
  4936.4 1068.17  4952.0 1065.26  4972.0 1064.95  4982.0 1064.00  4992.0 1061.87
  5000.0 1060.99  5000.3 1060.49  5003.8 1060.49  5004.0 1060.99  5022.1 1064.34
  5042.1 1065.63  5202.2 1065.86  5222.3 1066.19  5252.4 1068.26  5282.3 1071.10
  5309.2 1072.03  5332.4 1072.70  5342.4 1073.83  5382.4 1074.16  5538.0 1079.73
#Mann=5,-1,0
  4696.0    0.12       0  5000.0    0.07       0  5004.0    0.12       0
  5252.4    0.05       0  5309.2    0.12       0
Bank Sta=5000,5004
Exp/Cntr=0.3,0.1

Type RM Length L Ch R = 1,17215,465,465,465
BEGIN DESCRIPTION:
COTTONWOOD CREEK 01 38.0
END DESCRIPTION:
XS GIS Cut Line= 3
      2861621.19     10180450.61      2861630.65     10180212.23
      2861632.53     10179646.40
#Sta/Elev= 30
  4689.2 1094.05  4696.7 1094.00  4724.3 1091.96  4766.8 1089.55  4841.3 1082.96
  4924.8 1075.03  4936.6 1074.28  4966.9 1072.20  4976.9 1069.25  4986.9 1063.46
  4994.9 1058.09  4995.1 1057.59  4998.6 1057.59  4998.9 1058.09  5016.9 1061.03
  5029.1 1059.92  5036.9 1059.94  5056.9 1062.15  5076.9 1062.44  5096.9 1062.59
  5126.9 1061.93  5156.9 1062.30  5186.9 1061.64  5236.9 1063.50  5266.9 1065.80
  5306.9 1067.10  5406.9 1071.46  5426.9 1072.83  5456.9 1073.65  5493.6 1075.39
#Mann=7,-1,0
  4689.2    0.12       0  4724.3    0.05       0  4841.3    0.12       0
  4936.6    0.05       0  4994.9    0.05       0  4998.9    0.05       0
  5029.1    0.12       0
Bank Sta=4994.9,4998.9
Exp/Cntr=0.3,0.1

Type RM Length L Ch R = 1,16750,458,458,458
BEGIN DESCRIPTION:
COTTONWOOD CREEK 01 37.0
END DESCRIPTION:
XS GIS Cut Line= 3
      2861895.45     10180410.86      2862025.44     10180006.44
      2862024.09     10179650.44
#Sta/Elev= 30
  4486.1 1083.99  4516.7 1081.92  4533.4 1081.57  4557.3 1079.12  4704.4 1068.19
  4731.3 1066.55  4788.3 1064.68  4809.4 1063.05  4819.9 1063.03  4851.4 1061.32
  4859.7 1060.32  4864.9 1060.59  4882.9 1058.10  4896.0 1057.86  4944.2 1057.84
  4974.2 1057.06  4984.2 1056.62  5002.2 1053.60  5002.5 1053.10  5006.0 1053.10
  5006.2 1053.60  5034.2 1061.17  5054.2 1062.12  5084.2 1066.45  5114.2 1072.61
  5124.2 1076.17  5184.2 1086.00  5214.2 1090.37  5234.2 1092.07  5266.9 1093.65
#Mann=5,-1,0
  4486.1    0.12       0  4516.7    0.05       0  4896.0    0.12       0
  5002.2    0.07       0  5006.2    0.12       0
Bank Sta=5002.2,5006.2
Exp/Cntr=0.3,0.1

Type RM Length L Ch R = 1,16292,251,251,251
BEGIN DESCRIPTION:
COTTONWOOD CREEK 01 36.0
END DESCRIPTION:
XS GIS Cut Line= 3
      2862069.51     10180371.09      2862201.89     10180197.10
      2862531.17     10180018.35
#Sta/Elev= 30
  4703.6 1073.58  4706.4 1072.48  4713.6 1071.67  4750.1 1069.48  4770.9 1067.49
  4791.7 1064.39  4841.6 1059.78  4949.3 1055.90  4986.1 1050.62  4992.8 1048.55
  4993.1 1048.05  4996.8 1048.55  5007.9 1048.74  5024.1 1052.57  5045.9 1053.78
  5059.1 1056.39  5074.5 1059.55  5084.0 1060.28  5111.5 1064.84  5127.7 1066.65
  5133.4 1068.26  5149.5 1068.55  5155.2 1070.06  5171.4 1069.29  5177.1 1070.72
  5209.4 1072.98  5215.1 1074.21  5258.8 1078.94  5280.7 1080.89  5296.9 1081.08
#Mann=4,-1,0
  4703.6    0.12       0  4992.8    0.05       0  4996.8    0.12       0
  5059.1    0.12       0
Bank Sta=4992.8,4996.8
Exp/Cntr=0.3,0.1

Type RM Length L Ch R = 1,16041,434,434,434
BEGIN DESCRIPTION:
COTTONWOOD CREEK 01 35.0
END DESCRIPTION:
XS GIS Cut Line= 3
      2862152.68     10180556.52      2862483.73     10180301.13
      2862616.15     10180200.88
#Sta/Elev= 30
  4710.3 1069.76  4728.6 1069.20  4786.6 1064.43  4792.9 1064.60  4815.1 1062.68
  4871.7 1059.82  4907.0 1056.40  4915.2 1054.24  4928.8 1052.80  4979.3 1050.23
  4985.8 1049.54  5000.3 1046.27  5004.6 1045.95  5004.9 1045.45  5008.4 1045.45
  5008.6 1045.95  5021.1 1050.24  5064.6 1051.42  5085.5 1053.24  5130.9 1055.86
  5135.3 1057.11  5149.8 1058.31  5156.1 1059.53  5178.9 1062.08  5193.5 1065.78
  5214.3 1066.12  5220.6 1067.22  5243.4 1068.97  5249.7 1069.97  5294.5 1071.75
#Mann=3,-1,0
  4710.3    0.05       0  5004.6    0.05       0  5008.6    0.12       0
Bank Sta=5004.6,5008.6
Exp/Cntr=0.3,0.1

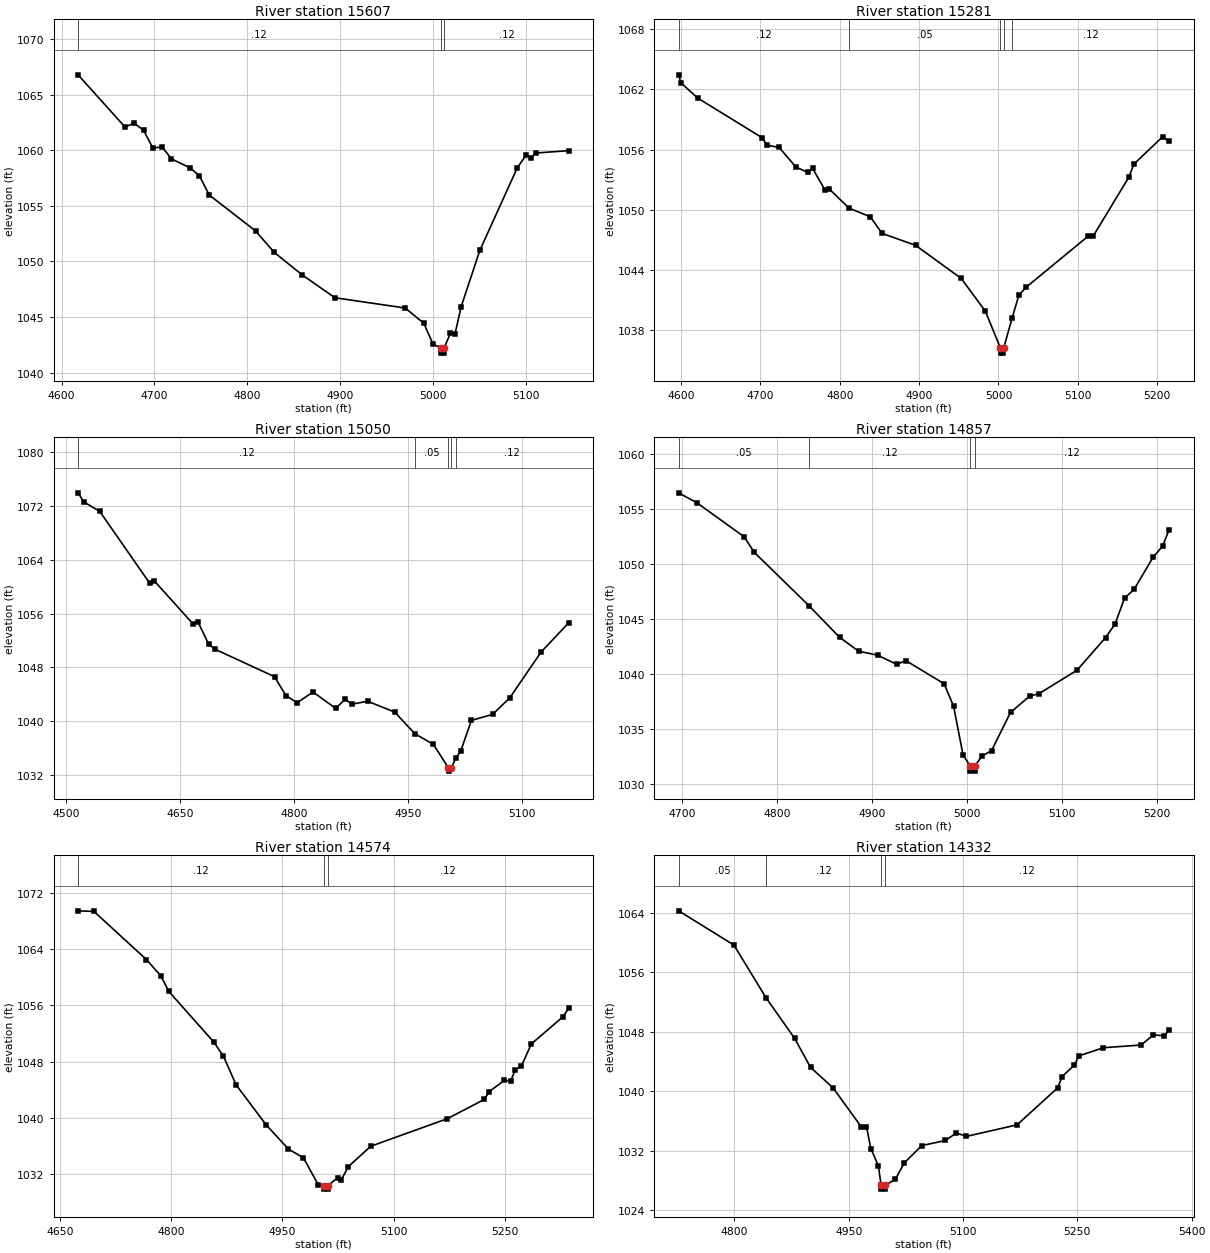
Type RM Length L Ch R = 1,15607,326,326,326
BEGIN DESCRIPTION:
COTTONWOOD CREEK 01 34.0
END DESCRIPTION:
XS GIS Cut Line= 3
      2862155.65     10180753.11      2862430.77     10180783.48
      2862680.45     10180753.21
#Sta/Elev= 30
  4617.8 1066.78  4668.3 1062.09  4678.2 1062.43  4688.3 1061.80  4698.3 1060.21
  4708.4 1060.28  4718.4 1059.22  4738.6 1058.41  4748.6 1057.69  4759.1 1055.97
  4809.0 1052.74  4829.1 1050.81  4859.3 1048.78  4894.5 1046.73  4970.1 1045.81
  4990.2 1044.44  5000.3 1042.53  5008.3 1042.25  5008.6 1041.75  5012.1 1041.75
  5012.3 1042.25  5018.8 1043.52  5023.9 1043.51  5030.5 1045.94  5050.6 1051.00
  5090.9 1058.42  5100.7 1059.59  5105.7 1059.34  5111.1 1059.75  5146.1 1059.96
#Mann=3,-1,0
  4617.8    0.12       0  5008.3    0.07       0  5012.3    0.12       0
Bank Sta=5008.3,5012.3
Exp/Cntr=0.3,0.1

Type RM Length L Ch R = 1,15281,231,231,231
BEGIN DESCRIPTION:
Mapping XS 3ded1c4f
END DESCRIPTION:
XS GIS Cut Line= 2
      2862237.83     10181309.32      2862756.08     10180972.65
#Sta/Elev= 30
  4597.0 1063.46  4599.8 1062.67  4620.9 1061.15  4701.8 1057.21  4708.5 1056.45
  4723.7 1056.22  4744.8 1054.26  4759.9 1053.73  4765.9 1054.13  4781.0 1052.02
  4787.0 1052.06  4811.8 1050.17  4838.4 1049.31  4853.5 1047.65  4895.7 1046.46
  4953.1 1043.16  4983.4 1039.91  5002.5 1036.22  5002.7 1035.72  5006.2 1035.72
  5006.5 1036.22  5017.3 1039.24  5025.6 1041.48  5034.7 1042.28  5113.2 1047.39
  5119.1 1047.35  5164.6 1053.30  5170.5 1054.55  5206.8 1057.28  5215.0 1056.84
#Mann=5,-1,0
  4597.0    0.12       0  4811.8    0.05       0  5002.5    0.05       0
  5006.5    0.05       0  5017.3    0.12       0
Bank Sta=5002.5,5006.5
Exp/Cntr=0.3,0.1

Type RM Length L Ch R = 1,15050,193,193,193
BEGIN DESCRIPTION:
COTTONWOOD CREEK 01 33.0
END DESCRIPTION:
XS GIS Cut Line= 3
      2862305.64     10181553.14      2862705.25     10181279.00
      2862805.66     10181153.15
#Sta/Elev= 30
  4515.4 1073.95  4522.9 1072.60  4543.9 1071.20  4609.5 1060.54  4615.6 1060.87
  4666.4 1054.51  4673.1 1054.78  4687.3 1051.45  4696.2 1050.67  4774.0 1046.62
  4788.9 1043.82  4803.8 1042.74  4824.7 1044.35  4854.5 1041.90  4867.1 1043.31
  4875.5 1042.52  4896.5 1042.97  4932.3 1041.35  4958.7 1038.14  4983.1 1036.55
  5002.9 1033.08  5003.2 1032.58  5006.9 1033.08  5012.6 1034.51  5019.3 1035.62
  5033.1 1040.12  5061.0 1041.01  5083.4 1043.44  5125.0 1050.30  5161.0 1054.60
#Mann=5,-1,0
  4515.4    0.12       0  4958.7    0.05       0  5002.9    0.05       0
  5006.9    0.05       0  5012.6    0.12       0
Bank Sta=5002.9,5006.9
Exp/Cntr=0.3,0.1

Type RM Length L Ch R = 1,14857,283,283,283
BEGIN DESCRIPTION:
Mapping XS a232ea28
END DESCRIPTION:
XS GIS Cut Line= 2
      2862860.15     10181672.48      2862863.91     10181156.19
#Sta/Elev= 30
  4696.5 1056.51  4715.9 1055.59  4765.6 1052.50  4775.9 1051.11  4833.7 1046.23
  4865.9 1043.36  4885.9 1042.09  4905.9 1041.73  4925.9 1040.90  4935.9 1041.22
  4975.9 1039.13  4985.9 1037.09  4995.9 1032.64  5003.2 1031.67  5003.6 1031.17
  5008.1 1031.17  5008.5 1031.67  5015.9 1032.54  5025.9 1033.04  5045.9 1036.52
  5065.9 1037.99  5075.9 1038.23  5115.9 1040.36  5145.9 1043.33  5155.9 1044.56
  5165.9 1046.92  5175.9 1047.71  5195.9 1050.64  5205.9 1051.65  5212.8 1053.16
#Mann=4,-1,0
  4696.5    0.05       0  4833.7    0.12       0  5003.2    0.07       0
  5008.5    0.12       0
Bank Sta=5003.2,5008.5
Exp/Cntr=0.3,0.1

Type RM Length L Ch R = 1,14574,242,242,242
BEGIN DESCRIPTION:
COTTONWOOD CREEK 01 32.0
END DESCRIPTION:
XS GIS Cut Line= 3
      2863185.49     10181674.41      2863128.75     10181234.07
      2862955.69     10181103.12
#Sta/Elev= 30
  4674.6 1069.48  4696.1 1069.39  4766.7 1062.54  4786.1 1060.22  4796.9 1058.00
  4857.4 1050.80  4870.6 1048.77  4887.6 1044.69  4928.0 1039.00  4958.2 1035.54
  4978.4 1034.29  4998.6 1030.41  5005.9 1030.34  5006.4 1029.84  5010.9 1029.84
  5011.3 1030.34  5024.5 1031.47  5029.5 1031.19  5038.9 1033.05  5069.1 1035.95
  5172.2 1039.87  5222.2 1042.62  5228.5 1043.72  5249.3 1045.34  5257.6 1045.24
  5263.8 1046.82  5272.1 1047.36  5285.4 1050.51  5328.3 1054.41  5335.6 1055.58
#Mann=3,-1,0
  4674.6    0.12       0  5005.9    0.07       0  5011.3    0.12       0
Bank Sta=5005.9,5011.3
Exp/Cntr=0.3,0.1

Type RM Length L Ch R = 1,14332,232,232,232
BEGIN DESCRIPTION:
COTTONWOOD CREEK 01 31.0
END DESCRIPTION:
XS GIS Cut Line= 3
      2863592.18     10181428.50      2863423.82     10181307.43
      2863040.28     10181099.60
#Sta/Elev= 30
  4726.8 1064.24  4799.3 1059.64  4841.5 1052.55  4879.0 1047.09  4899.9 1043.20
  4929.4 1040.45  4966.2 1035.24  4973.3 1035.21  4979.0 1032.28  4988.9 1029.98
  4992.5 1027.33  4992.9 1026.83  4997.4 1026.83  4997.9 1027.33  5011.3 1028.18
  5023.0 1030.37  5045.8 1032.68  5076.9 1033.37  5091.3 1034.38  5104.5 1033.92
  5170.9 1035.47  5224.3 1040.46  5230.0 1041.96  5246.2 1043.52  5251.9 1044.74
  5284.3 1045.84  5333.7 1046.20  5349.9 1047.57  5364.3 1047.43  5370.4 1048.25
#Mann=4,-1,0
  4726.8    0.05       0  4841.5    0.12       0  4992.5    0.07       0
  4997.9    0.12       0
Bank Sta=4992.5,4997.9
Exp/Cntr=0.3,0.1

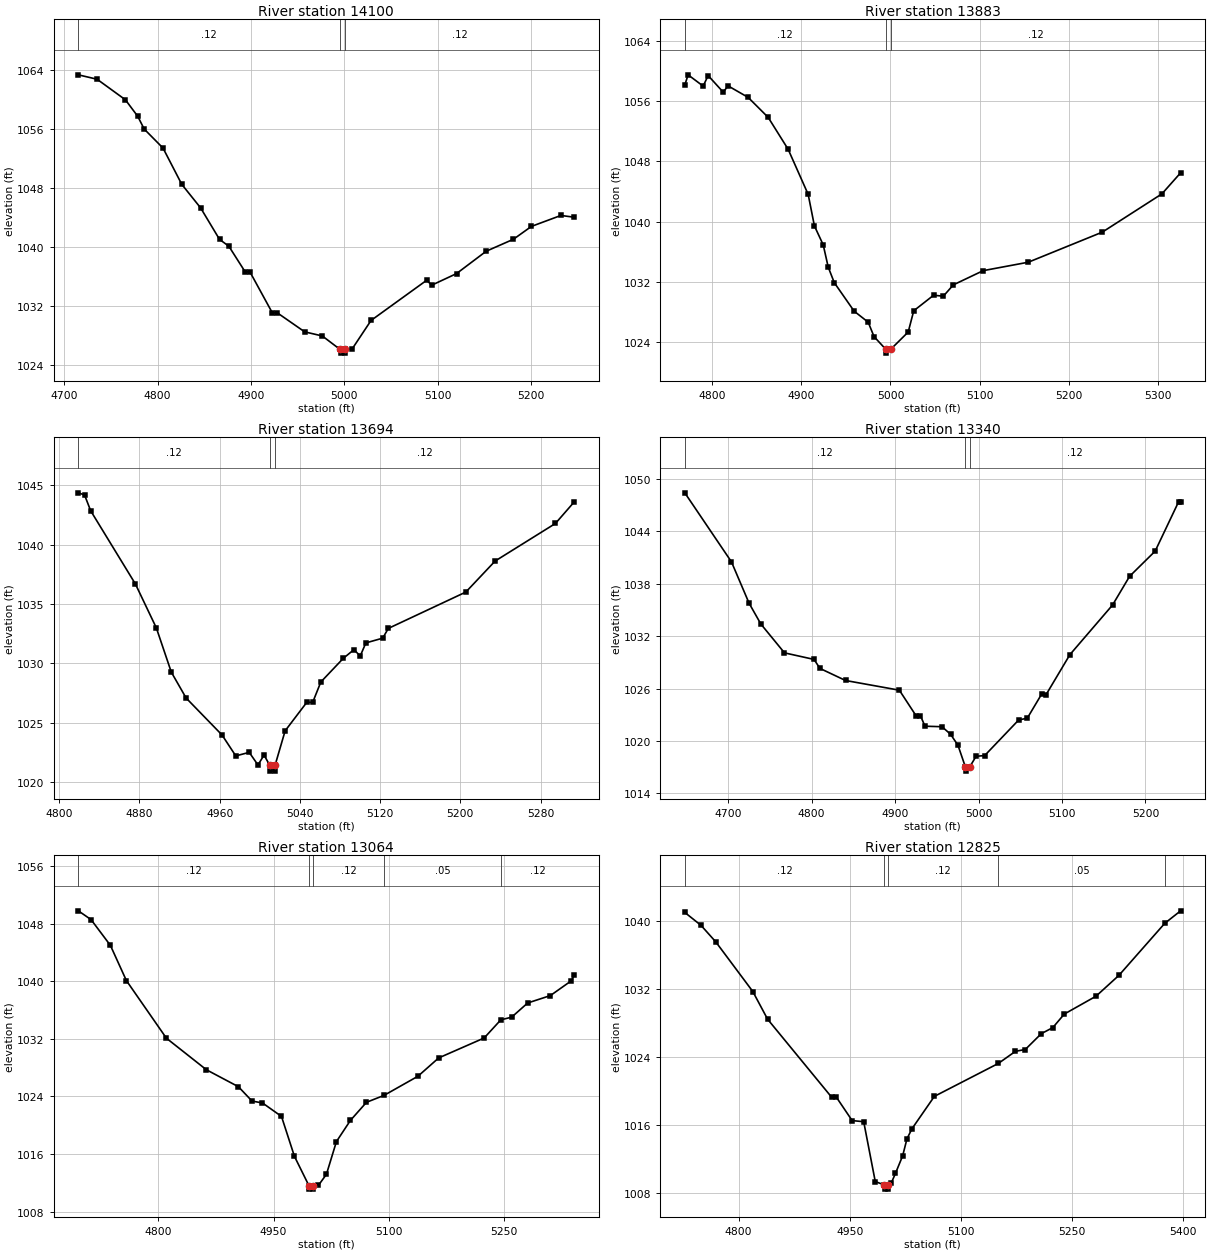
Type RM Length L Ch R = 1,14100,217,217,217
BEGIN DESCRIPTION:
Mapping XS 10000bfd
END DESCRIPTION:
XS GIS Cut Line= 3
      2863635.66     10181055.86      2863455.98     10181033.16
      2863111.70     10181095.58
#Sta/Elev= 30
  4715.1 1063.38  4735.2 1062.78  4765.5 1059.99  4778.7 1057.75  4785.6 1056.02
  4805.8 1053.43  4825.9 1048.50  4846.1 1045.30  4866.3 1041.03  4876.3 1040.10
  4893.8 1036.61  4898.9 1036.61  4922.9 1031.04  4928.0 1031.07  4957.5 1028.47
  4976.4 1027.91  4995.4 1026.08  4995.9 1025.58  5000.4 1025.58  5000.8 1026.08
  5008.3 1026.14  5028.6 1030.02  5088.3 1035.49  5093.4 1034.80  5120.1 1036.38
  5151.9 1039.42  5181.1 1041.05  5200.3 1042.79  5231.9 1044.28  5246.1 1044.04
#Mann=3,-1,0
  4715.1    0.12       0  4995.4    0.07       0  5000.8    0.12       0
Bank Sta=4995.4,5000.8
Exp/Cntr=0.3,0.1

Type RM Length L Ch R = 1,13883,189,189,189
BEGIN DESCRIPTION:
Mapping XS af3cfd71
END DESCRIPTION:
XS GIS Cut Line= 2
      2863486.21     10180747.55      2862986.87     10180993.44
#Sta/Elev= 30
  4769.1 1058.16  4772.8 1059.52  4789.7 1058.02  4795.3 1059.42  4812.2 1057.22
  4817.7 1058.05  4840.2 1056.52  4862.7 1053.86  4885.1 1049.62  4907.6 1043.62
  4914.6 1039.43  4924.5 1036.90  4930.1 1033.95  4936.9 1031.88  4959.2 1028.09
  4975.0 1026.62  4981.5 1024.71  4994.8 1023.01  4995.2 1022.51  5000.2 1023.01
  5019.9 1025.32  5026.1 1028.14  5048.4 1030.21  5059.3 1030.08  5070.6 1031.59
  5104.1 1033.48  5154.7 1034.60  5237.8 1038.60  5304.7 1043.69  5325.7 1046.49
#Mann=3,-1,0
  4769.1    0.12       0  4994.8    0.07       0  5000.2    0.12       0
Bank Sta=4994.8,5000.2
Exp/Cntr=0.3,0.1

Type RM Length L Ch R = 1,13694,354,354,354
BEGIN DESCRIPTION:
COTTONWOOD CREEK 01 30.0
END DESCRIPTION:
XS GIS Cut Line= 3
      2863304.66     10180603.78      2863114.28     10180735.85
      2862878.95     10180852.58
#Sta/Elev= 30
  4819.1 1044.36  4825.3 1044.18  4831.4 1042.85  4876.0 1036.69  4896.9 1032.99
  4911.8 1029.27  4926.6 1027.09  4962.4 1023.98  4976.1 1022.22  4989.5 1022.52
  4998.2 1021.46  5004.3 1022.29  5009.9 1021.44  5010.3 1020.94  5014.9 1020.94
  5015.3 1021.44  5025.3 1024.33  5046.9 1026.73  5052.8 1026.73  5060.9 1028.44
  5083.4 1030.44  5093.9 1031.16  5100.2 1030.63  5105.8 1031.73  5122.6 1032.13
  5128.2 1032.95  5205.5 1036.01  5234.7 1038.62  5294.8 1041.78  5313.5 1043.59
#Mann=3,-1,0
  4819.1    0.12       0  5009.9    0.07       0  5015.3    0.12       0
Bank Sta=5009.9,5015.3
Exp/Cntr=0.3,0.1

Type RM Length L Ch R = 1,13340,276,276,276
BEGIN DESCRIPTION:
Mapping XS 644c5821
END DESCRIPTION:
XS GIS Cut Line= 3
      2863327.37     10180560.29      2863187.38     10180425.98
      2862795.84     10180344.64
#Sta/Elev= 30
  4648.2 1048.39  4704.1 1040.49  4725.2 1035.76  4739.3 1033.38  4767.6 1030.08
  4803.0 1029.33  4810.1 1028.30  4840.7 1026.92  4905.2 1025.81  4925.3 1022.87
  4930.4 1022.90  4935.9 1021.69  4956.3 1021.63  4966.5 1020.77  4975.4 1019.51
  4984.2 1017.05  4984.6 1016.55  4989.6 1017.05  4997.1 1018.25  5007.4 1018.33
  5048.2 1022.41  5058.4 1022.60  5075.6 1025.36  5080.7 1025.26  5109.5 1029.88
  5160.6 1035.56  5181.0 1038.84  5211.6 1041.72  5239.6 1047.35  5242.1 1047.35
#Mann=3,-1,0
  4648.2    0.12       0  4984.2    0.07       0  4989.6    0.12       0
Bank Sta=4984.2,4989.6
Exp/Cntr=0.3,0.1

Type RM Length L Ch R = 1,13064,239,239,239
BEGIN DESCRIPTION:
COTTONWOOD CREEK 01 29.0
END DESCRIPTION:
XS GIS Cut Line= 3
      2863355.69     10180553.15      2863230.89     10180132.79
      2863060.65     10180013.62
#Sta/Elev= 30
  4695.6 1049.76  4712.2 1048.54  4737.4 1044.96  4758.2 1040.08  4810.4 1032.07
  4862.5 1027.69  4904.3 1025.33  4922.0 1023.34  4935.6 1023.08  4960.4 1021.21
  4977.3 1015.66  4996.1 1011.61  4996.5 1011.11  5001.1 1011.11  5001.6 1011.61
  5008.6 1011.64  5019.0 1013.17  5032.0 1017.71  5050.3 1020.66  5071.2 1023.17
  5094.1 1024.13  5138.3 1026.79  5165.3 1029.33  5224.6 1032.10  5246.3 1034.62
  5260.4 1034.99  5281.3 1036.96  5310.9 1037.99  5338.0 1040.03  5341.9 1040.79
#Mann=5,-1,0
  4695.6    0.12       0  4996.1    0.07       0  5001.6    0.12       0
  5094.1    0.05       0  5246.3    0.12       0
Bank Sta=4996.1,5001.6
Exp/Cntr=0.3,0.1

Type RM Length L Ch R = 1,12825,304,304,304
BEGIN DESCRIPTION:
COTTONWOOD CREEK 01 28.0
END DESCRIPTION:
XS GIS Cut Line= 3
      2863531.64     10180444.91      2863531.36     10180245.31
      2863291.43     10179841.51
#Sta/Elev= 30
  4727.3 1041.00  4749.1 1039.49  4769.1 1037.54  4819.1 1031.70  4839.1 1028.44
  4925.5 1019.27  4931.7 1019.30  4953.2 1016.52  4968.8 1016.39  4984.4 1009.35
  4996.5 1008.96  4996.9 1008.46  5001.5 1008.46  5002.0 1008.96  5005.8 1009.14
  5011.6 1010.30  5021.4 1012.38  5027.2 1014.38  5034.1 1015.58  5064.2 1019.37
  5150.5 1023.24  5173.7 1024.67  5186.9 1024.88  5208.6 1026.75  5224.0 1027.45
  5239.6 1029.05  5282.4 1031.15  5313.3 1033.60  5375.2 1039.72  5396.6 1041.19
#Mann=5,-1,0
  4727.3    0.12       0  4996.5    0.07       0  5002.0    0.12       0
  5150.5    0.05       0  5375.2    0.12       0
Bank Sta=4996.5,5002
Exp/Cntr=0.3,0.1

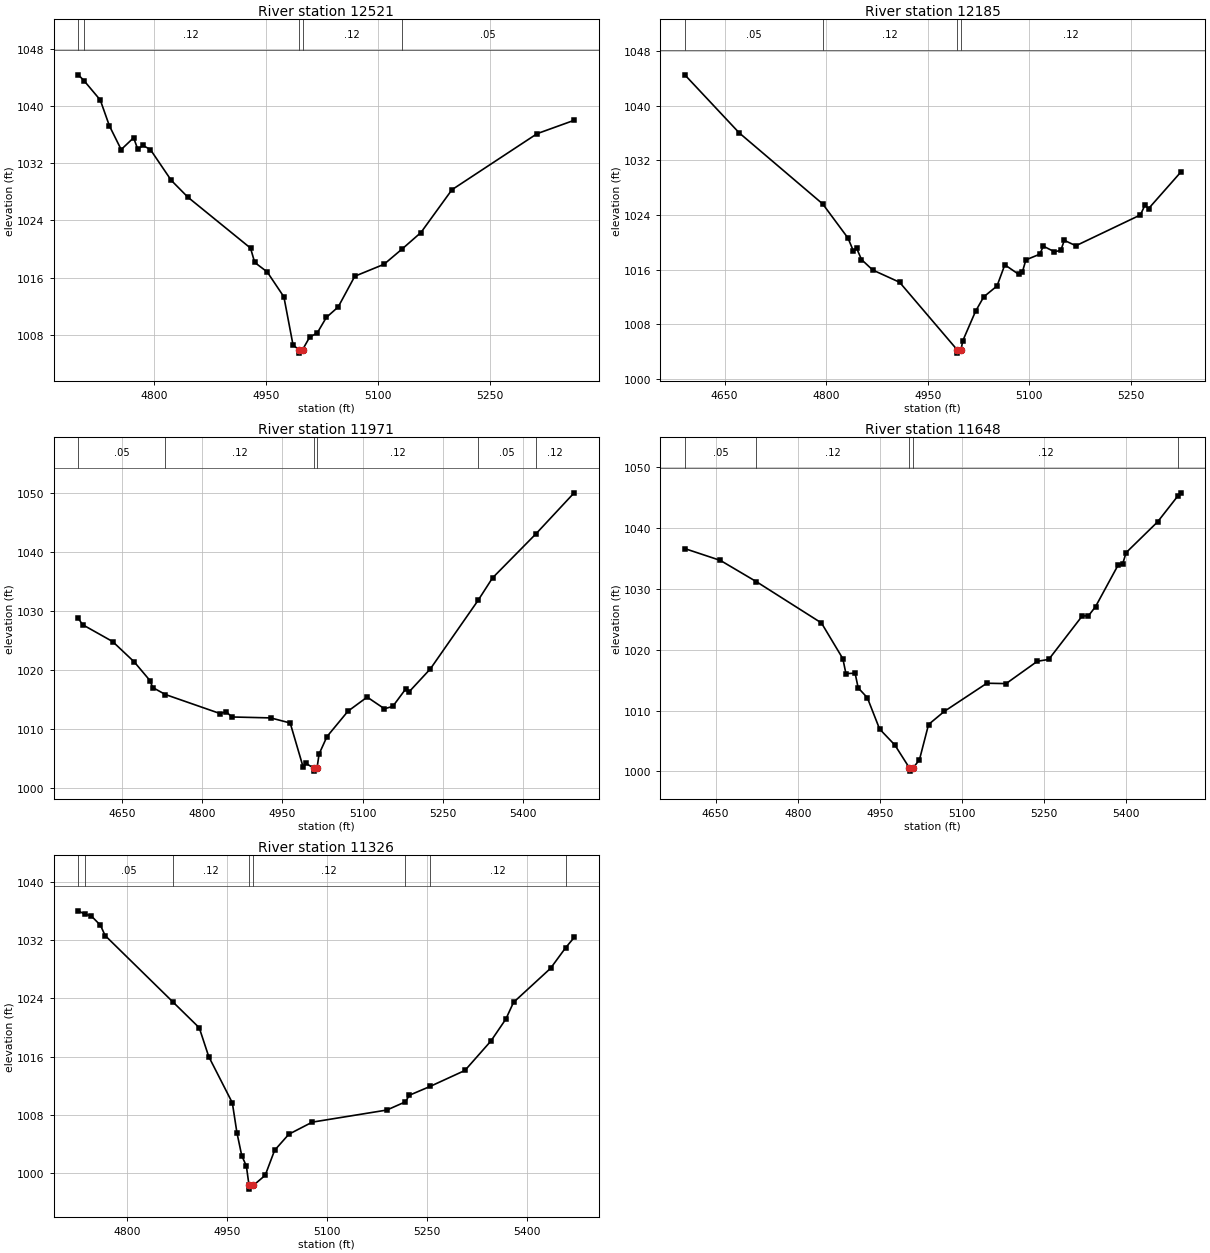
Type RM Length L Ch R = 1,12521,336,336,336
BEGIN DESCRIPTION:
COTTONWOOD CREEK 01 27.0
END DESCRIPTION:
XS GIS Cut Line= 3
      2863875.89     10180280.32      2863686.75     10179902.02
      2863495.73     10179754.50
#Sta/Elev= 30
  4698.5 1044.39  4706.3 1043.55  4727.9 1040.86  4740.1 1037.25  4755.9 1033.92
  4772.6 1035.58  4778.2 1033.94  4784.8 1034.51  4795.0 1033.93  4823.0 1029.61
  4845.3 1027.25  4929.2 1020.12  4934.8 1018.11  4951.5 1016.79  4973.9 1013.29
  4986.1 1006.58  4993.5 1005.91  4993.9 1005.41  4999.0 1005.91  5008.4 1007.64
  5018.6 1008.24  5030.8 1010.41  5046.6 1011.87  5068.9 1016.18  5108.0 1017.85
  5131.8 1019.95  5157.5 1022.30  5199.1 1028.30  5313.2 1036.15  5362.8 1038.02
#Mann=5,-1,0
  4698.5    0.05       0  4706.3    0.12       0  4993.5    0.07       0
  4999.0    0.12       0  5131.8    0.05       0
Bank Sta=4993.5,4999
Exp/Cntr=0.3,0.1

Type RM Length L Ch R = 1,12185,214,214,214
BEGIN DESCRIPTION:
Mapping XS 2eba2dd0
END DESCRIPTION:
XS GIS Cut Line= 3
      2864010.20     10180193.27      2864032.90     10179915.26
      2863883.85     10179486.99
#Sta/Elev= 30
  4591.3 1044.51  4671.7 1036.01  4795.0 1025.61  4832.3 1020.62  4840.2 1018.76
  4845.2 1019.10  4852.3 1017.47  4868.8 1015.94  4908.5 1014.15  4993.5 1004.27
  4994.0 1003.77  4999.4 1004.27  5001.8 1005.55  5020.8 1009.90  5032.9 1012.01
  5052.5 1013.60  5064.0 1016.70  5084.3 1015.32  5089.8 1015.59  5095.1 1017.42
  5115.6 1018.25  5120.9 1019.43  5137.2 1018.61  5146.7 1018.81  5151.9 1020.28
  5169.0 1019.49  5264.3 1024.00  5271.0 1025.44  5276.3 1024.92  5323.7 1030.24
#Mann=4,-1,0
  4591.3    0.05       0  4795.0    0.12       0  4993.5    0.07       0
  4999.4    0.12       0
Bank Sta=4993.5,4999.4
Exp/Cntr=0.3,0.1

Type RM Length L Ch R = 1,11971,323,323,323
BEGIN DESCRIPTION:
COTTONWOOD CREEK 01 26.0
END DESCRIPTION:
XS GIS Cut Line= 3
      2864159.63     10180136.59      2864214.49     10179780.96
      2864005.68     10179253.10
#Sta/Elev= 30
  4568.1 1028.81  4575.9 1027.74  4632.3 1024.87  4672.8 1021.41  4702.2 1018.25
  4707.2 1017.08  4731.1 1015.89  4833.5 1012.66  4844.8 1013.00  4854.9 1012.09
  4927.9 1011.93  4964.4 1011.07  4988.7 1003.57  4994.1 1004.21  5008.7 1003.41
  5009.2 1002.91  5014.6 1003.41  5018.4 1005.80  5033.2 1008.76  5072.5 1013.07
  5108.4 1015.46  5140.7 1013.48  5156.3 1013.88  5180.6 1016.85  5186.0 1016.27
  5226.7 1020.25  5315.8 1031.84  5342.9 1035.66  5423.3 1043.05  5495.6 1050.08
#Mann=6,-1,0
  4568.1    0.05       0  4731.1    0.12       0  5008.7    0.07       0
  5014.6    0.12       0  5315.8    0.05       0  5423.3    0.12       0
Bank Sta=5008.7,5014.6
Exp/Cntr=0.3,0.1

Type RM Length L Ch R = 1,11648,322,322,322
BEGIN DESCRIPTION:
Mapping XS 98abe753
END DESCRIPTION:
XS GIS Cut Line= 5
      2864651.45     10179922.87      2864441.47     10179502.91
      2864244.75     10179332.67      2864248.53     10179332.67
      2864116.14     10179222.97
#Sta/Elev= 30
  4593.8 1036.57  4658.8 1034.63  4724.4 1031.15  4843.3 1024.37  4882.4 1018.51
  4888.0 1016.07  4904.8 1016.12  4910.4 1013.72  4927.1 1012.11  4949.5 1006.97
  4977.4 1004.34  5004.1 1000.56  5004.6 1000.06  5010.4 1000.56  5022.2 1001.90
  5038.9 1007.71  5067.5 1009.85  5145.4 1014.48  5180.5 1014.42  5237.5 1018.08
  5258.4 1018.39  5319.6 1025.53  5330.8 1025.53  5343.8 1027.04  5385.4 1033.92
  5393.3 1034.06  5399.7 1035.91  5457.1 1040.95  5494.8 1045.28  5499.2 1045.72
#Mann=5,-1,0
  4593.8    0.05       0  4724.4    0.12       0  5004.1    0.07       0
  5010.4    0.12       0  5494.8    0.05       0
Bank Sta=5004.1,5010.4
Exp/Cntr=0.3,0.1

Type RM Length L Ch R = 1,11326,351,351,351
BEGIN DESCRIPTION:
COTTONWOOD CREEK 01 25.0
END DESCRIPTION:
XS GIS Cut Line= 3
      2864914.33     10179561.52      2864649.54     10179287.27
      2864324.17     10179124.58
#Sta/Elev= 30
  4726.5 1036.03  4736.5 1035.55  4745.6 1035.36  4759.8 1034.04  4766.7 1032.64
  4868.3 1023.54  4908.2 1019.97  4922.4 1016.02  4957.9 1009.66  4964.8 1005.56
  4972.0 1002.42  4979.0 1000.97  4983.0  998.31  4983.5  997.81  4989.3  998.31
  5007.3  999.71  5021.4 1003.14  5042.8 1005.35  5078.0 1007.01  5190.0 1008.67
  5218.0 1009.80  5223.8 1010.70  5255.2 1011.92  5307.4 1014.11  5346.5 1018.16
  5368.9 1021.17  5380.4 1023.46  5436.0 1028.13  5458.6 1030.95  5471.5 1032.37
#Mann=8,-1,0
  4726.5    0.12       0  4736.5    0.05       0  4868.3    0.12       0
  4983.0    0.07       0  4989.3    0.12       0  5218.0    0.05       0
  5255.2    0.12       0  5458.6    0.05       0
Bank Sta=4983,4989.3
Exp/Cntr=0.3,0.1