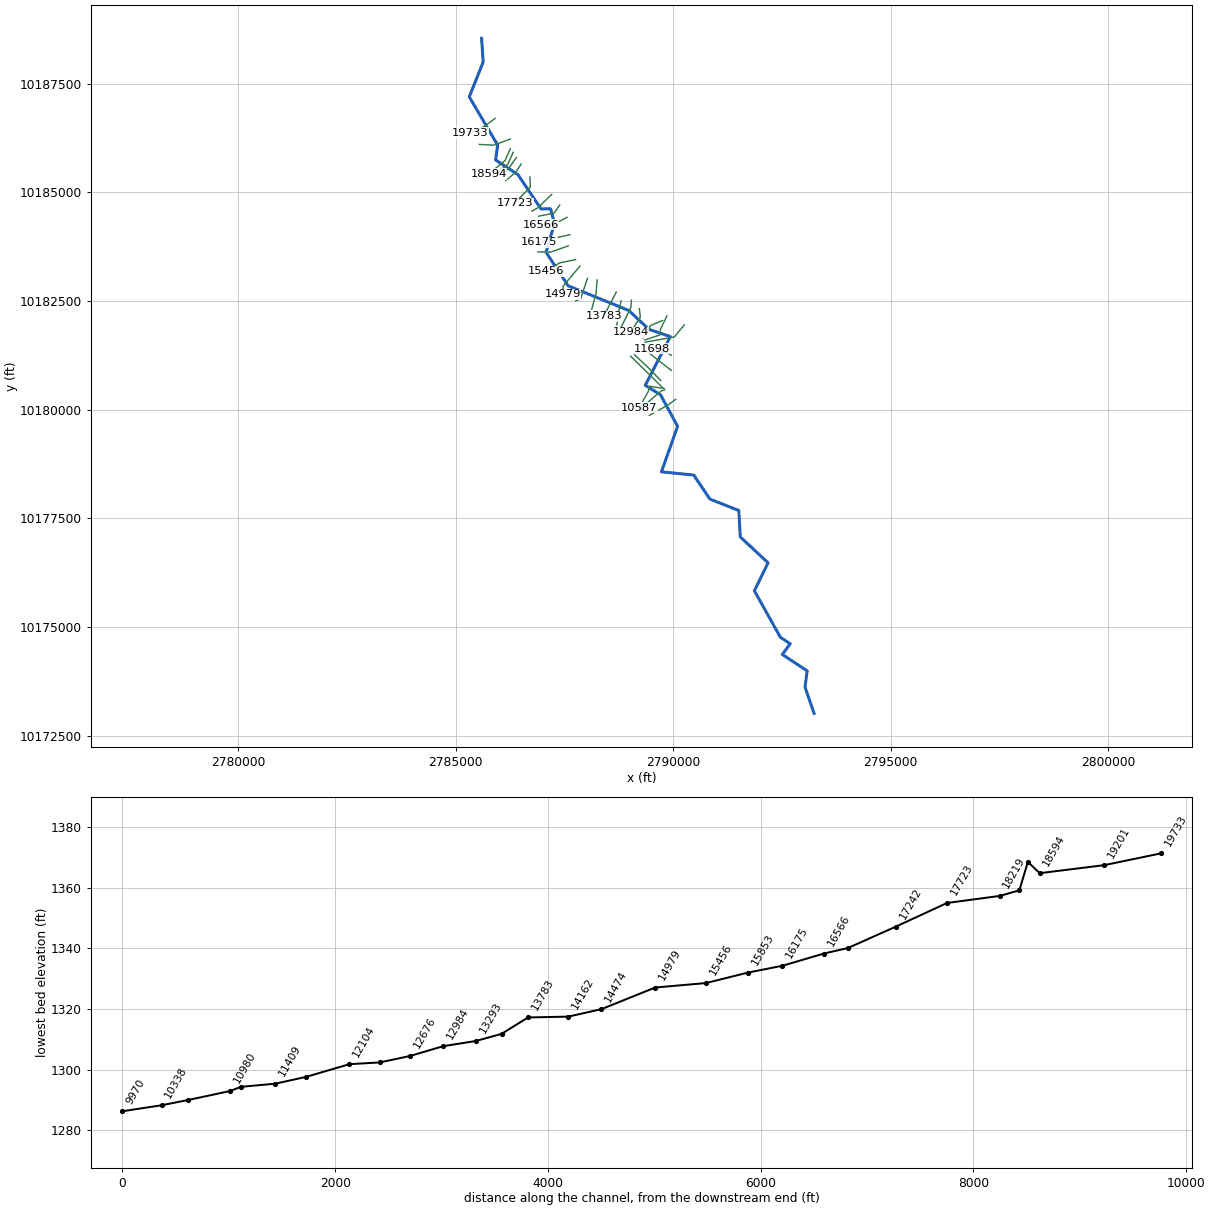
--- COTTONWOOD CREEK 02.prj (project) ---

Proj Title=COTTONWOOD CREEK 02 Base Level Engineering
Current Plan=p01
Default Exp/Contr=0.3,0.1
English Units
Geom File=g01
Flow File=f01
Plan File=p01
BEGIN DESCRIPTION:
COTTONWOOD CREEK 02
END DESCRIPTION:

--- COTTONWOOD CREEK 02.p01 (plan) ---

Plan Title=Multiple Run
Short Identifier=Multiple
Geom File=g01
Flow File=f01
Subcritical Flow
K Sum by GR= 0
Std Step Tol= 0.01
Critical Tol= 0.01
Num of Std Step Trials= 20
Max Error Tol= 0.3
Flow Tol Ratio= 0.001
Split Flow NTrial= 30
Split Flow Tol= 0.02
Split Flow Ratio= 0.02
Log Output Level= 0
Friction Slope Method= 1
Unsteady Friction Slope Method= 2
Unsteady Bridges Friction Slope Method= 1
Parabolic Critical Depth
Global Vel Dist=  1 , 1 , 1
Global Log Level= 0
CheckData=True
Encroach Param= -1, 0, 0, 0
BEGIN DESCRIPTION:
Multiple Run
END DESCRIPTION:

--- COTTONWOOD CREEK 02.f01 (steady flow) ---

Flow Title=Multiple
Number of Profiles=7
Profile Names=10-year,25-year,50-year,1pct_min,100-year,1pct_plu,500-year
River Rch & RM= COTTONWOOD CREEK,Reach-1,19733
     418     675    1524    1256    2161    3719    3177
River Rch & RM= COTTONWOOD CREEK,Reach-1,14979
     611    1015    2113    1622    3009    5581    4380
River Rch & RM= COTTONWOOD CREEK,Reach-1,10587
     791    1329    2918    2272    4195    7746    6080
River Rch & RM= COTTONWOOD CREEK,Reach-1,9488
    1181    2050    4078    2933    5888   11821    8463
Boundary for River Rch & Prof#=COTTONWOOD CREEK,Reach-1,1
Up Type=0
Dn Type=3
Dn Slope=0.005
Boundary for River Rch & Prof#=COTTONWOOD CREEK,Reach-1,2
Up Type=0
Dn Type=3
Dn Slope=0.005
Boundary for River Rch & Prof#=COTTONWOOD CREEK,Reach-1,3
Up Type=0
Dn Type=3
Dn Slope=0.005
Boundary for River Rch & Prof#=COTTONWOOD CREEK,Reach-1,4
Up Type=0
Dn Type=3
Dn Slope=0.005
Boundary for River Rch & Prof#=COTTONWOOD CREEK,Reach-1,5
Up Type=0
Dn Type=3
Dn Slope=0.005
Boundary for River Rch & Prof#=COTTONWOOD CREEK,Reach-1,6
Up Type=0
Dn Type=3
Dn Slope=0.005
Boundary for River Rch & Prof#=COTTONWOOD CREEK,Reach-1,7
Up Type=0
Dn Type=3
Dn Slope=0.005

--- COTTONWOOD CREEK 02.g01 (geometry) ---

Geom Title=Existing Conditions

River Reach=COTTONWOOD CREEK,Reach-1
Reach XY= 30
      2785596.00     10188545.00      2785631.50     10188001.00
      2785312.00     10187198.00      2785965.00     10186089.00
      2785919.00     10185747.00      2786429.00     10185411.00
      2786963.25     10184619.00      2787181.50     10184623.00
      2787271.25     10184286.00      2787077.25     10183622.00
      2787585.25     10182851.00      2788981.00     10182283.00
      2789436.50     10181852.00      2789935.00     10181682.00
      2789357.00     10180562.00      2789709.25     10180344.00
      2790100.75     10179619.00      2789730.00     10178571.00
      2790473.75     10178497.00      2790843.00     10177945.00
      2791508.75     10177681.00      2791542.50     10177074.00
      2792181.50     10176478.00      2791867.00     10175835.00
      2792464.25     10174765.00      2792690.00     10174616.00
      2792508.75     10174370.00      2793080.00     10173992.00
      2793031.50     10173622.00      2793237.50     10173014.00

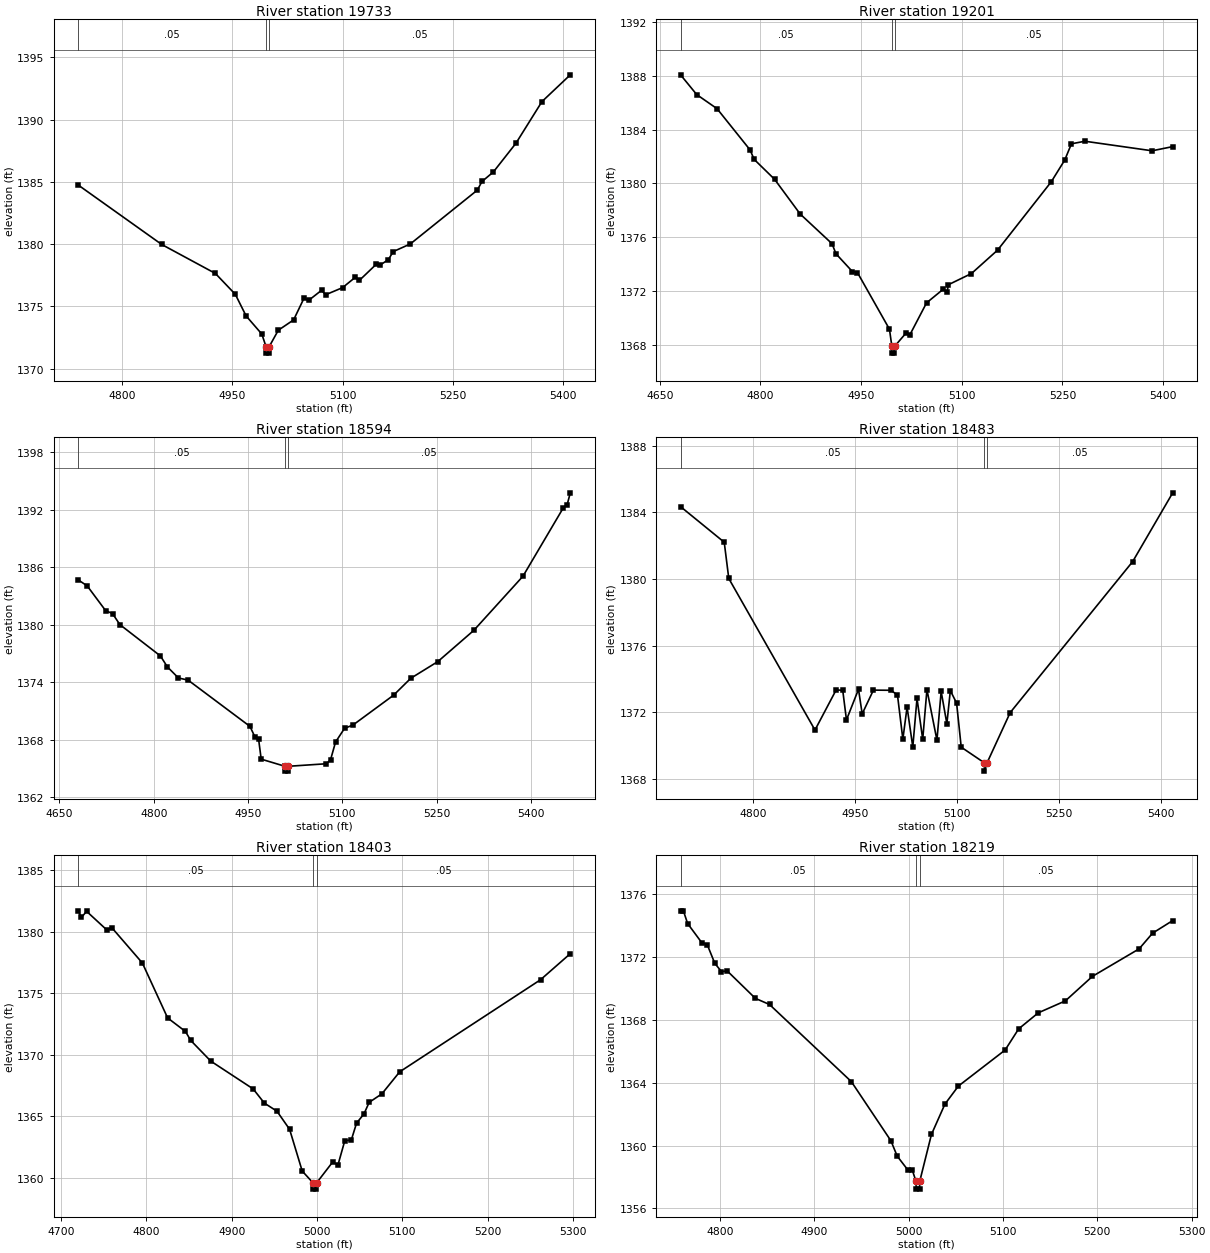
Type RM Length L Ch R = 1,19733,532,532,532
BEGIN DESCRIPTION:
COTTONWOOD CREEK 02 42.0
END DESCRIPTION:
XS GIS Cut Line= 3
      2785905.70     10186703.12      2785658.87     10186518.74
      2785330.66     10186368.65
#Sta/Elev= 30
  4740.5 1384.75  4854.1 1379.97  4927.1 1377.64  4954.2 1375.96  4968.8 1374.23
  4990.2 1372.77  4996.0 1371.74  4996.2 1371.24  4999.7 1371.24  5000.0 1371.74
  5012.6 1373.08  5033.4 1373.91  5047.5 1375.65  5053.9 1375.48  5071.4 1376.29
  5076.9 1375.93  5099.9 1376.50  5117.4 1377.34  5122.9 1377.09  5145.9 1378.39
  5151.4 1378.33  5162.1 1378.75  5168.9 1379.40  5192.0 1380.01  5283.0 1384.33
  5289.5 1385.03  5305.0 1385.80  5335.6 1388.10  5371.0 1391.45  5409.5 1393.60
#Mann=3,-1,0
  4740.5    0.05       0  4996.0    0.05       0  5000.0    0.05       0
Bank Sta=4996,5000
Exp/Cntr=0.3,0.1

Type RM Length L Ch R = 1,19201,607,607,607
BEGIN DESCRIPTION:
COTTONWOOD CREEK 02 41.0
END DESCRIPTION:
XS GIS Cut Line= 3
      2786252.66     10186226.76      2785876.60     10186086.57
      2785545.04     10186104.71
#Sta/Elev= 30
  4680.9 1388.07  4705.0 1386.60  4735.3 1385.55  4784.4 1382.49  4790.6 1381.78
  4821.0 1380.30  4859.1 1377.72  4906.6 1375.51  4912.5 1374.76  4936.9 1373.44
  4944.5 1373.36  4992.2 1369.15  4995.8 1367.87  4996.1 1367.37  4999.6 1367.37
  4999.8 1367.87  5017.2 1368.88  5022.5 1368.72  5047.5 1371.11  5072.5 1372.13
  5077.9 1371.90  5080.1 1372.46  5114.4 1373.29  5153.3 1375.03  5233.4 1380.12
  5253.4 1381.73  5263.4 1382.94  5283.5 1383.13  5383.6 1382.42  5414.3 1382.73
#Mann=3,-1,0
  4680.9    0.05       0  4995.8    0.05       0  4999.8    0.05       0
Bank Sta=4995.8,4999.8
Exp/Cntr=0.3,0.1

Type RM Length L Ch R = 1,18594,111,111,111
BEGIN DESCRIPTION:
COTTONWOOD CREEK 02 40.0
END DESCRIPTION:
XS GIS Cut Line= 3
      2786255.68     10186003.11      2786137.22     10185735.22
      2785759.23     10185422.97
#Sta/Elev= 30
  4679.7 1384.68  4694.1 1384.05  4723.4 1381.47  4734.4 1381.16  4746.1 1380.01
  4810.6 1376.74  4821.8 1375.59  4839.3 1374.44  4854.6 1374.22  4953.1 1369.39
  4961.3 1368.25  4966.8 1368.09  4971.0 1365.97  5009.1 1365.22  5009.4 1364.72
  5012.9 1364.72  5013.1 1365.22  5074.9 1365.49  5081.4 1365.91  5089.3 1367.75
  5103.6 1369.18  5117.3 1369.54  5181.8 1372.65  5209.1 1374.41  5252.1 1376.15
  5309.4 1379.41  5387.6 1385.06  5451.4 1392.15  5457.9 1392.52  5462.9 1393.76
#Mann=3,-1,0
  4679.7    0.05       0  5009.1    0.05       0  5013.1    0.05       0
Bank Sta=5009.1,5013.1
Exp/Cntr=0.3,0.1

Type RM Length L Ch R = 1,18483,80,80,80
BEGIN DESCRIPTION:
Mapping XS 461c03f7
END DESCRIPTION:
XS GIS Cut Line= 4
      2786320.32     10185921.62      2786193.31     10185639.55
      2786122.38     10185586.77      2785851.86     10185405.32
#Sta/Elev= 30
  4693.3 1384.35  4757.5 1382.21  4764.2 1380.03  4890.9 1370.92  4922.0 1373.33
  4931.7 1373.31  4937.2 1371.53  4954.9 1373.37  4960.3 1371.89  4976.8 1373.32
  5002.7 1373.31  5012.2 1373.02  5020.1 1370.37  5026.3 1372.30  5034.7 1369.90
  5040.9 1372.82  5049.3 1370.36  5055.5 1373.35  5070.2 1370.31  5076.4 1373.24
  5084.8 1371.30  5089.9 1373.29  5099.1 1372.54  5105.9 1369.89  5139.9 1368.95
  5140.1 1368.45  5143.9 1368.95  5177.9 1371.97  5358.0 1381.05  5416.8 1385.18
#Mann=3,-1,0
  4693.3    0.05       0  5139.9    0.03       0  5143.9    0.05       0
Bank Sta=5139.9,5143.9
Exp/Cntr=0.3,0.1

Type RM Length L Ch R = 1,18403,184,184,184
BEGIN DESCRIPTION:
Mapping XS 82d46187
END DESCRIPTION:
XS GIS Cut Line= 3
      2786392.89     10185801.19      2786211.45     10185542.23
      2785997.02     10185393.78
#Sta/Elev= 30
  4719.9 1381.69  4723.7 1381.15  4729.8 1381.65  4753.3 1380.15  4759.4 1380.32
  4795.2 1377.45  4824.8 1372.99  4845.7 1371.89  4851.9 1371.16  4875.4 1369.48
  4925.1 1367.22  4938.2 1366.07  4953.0 1365.41  4967.8 1363.94  4982.6 1360.55
  4995.4 1359.58  4995.7 1359.08  4999.2 1359.08  4999.4 1359.58  5018.4 1361.29
  5024.5 1361.04  5032.5 1363.01  5040.2 1363.08  5046.3 1364.44  5055.0 1365.19
  5061.1 1366.13  5076.0 1366.82  5096.9 1368.61  5262.0 1376.09  5296.9 1378.21
#Mann=3,-1,0
  4719.9    0.05       0  4995.4    0.05       0  4999.4    0.05       0
Bank Sta=4995.4,4999.4
Exp/Cntr=0.3,0.1

Type RM Length L Ch R = 1,18219,496,496,496
BEGIN DESCRIPTION:
COTTONWOOD CREEK 02 39.0
END DESCRIPTION:
XS GIS Cut Line= 3
      2786505.68     10185653.10      2786369.75     10185453.00
      2786153.73     10185275.02
#Sta/Elev= 30
  4758.1 1374.94  4761.1 1374.94  4765.6 1374.13  4780.5 1372.92  4786.5 1372.77
  4794.4 1371.60  4801.5 1371.07  4807.5 1371.12  4837.4 1369.37  4852.4 1368.98
  4939.2 1364.07  4981.1 1360.31  4987.8 1359.33  4999.2 1358.44  5003.8 1358.44
  5007.7 1357.73  5008.0 1357.23  5011.5 1357.23  5011.7 1357.73  5024.1 1360.71
  5038.4 1362.64  5052.7 1363.79  5102.2 1366.08  5116.6 1367.43  5137.4 1368.45
  5166.1 1369.21  5194.8 1370.77  5244.3 1372.52  5258.6 1373.52  5279.9 1374.32
#Mann=3,-1,0
  4758.1    0.05       0  5007.7    0.05       0  5011.7    0.05       0
Bank Sta=5007.7,5011.7
Exp/Cntr=0.3,0.1

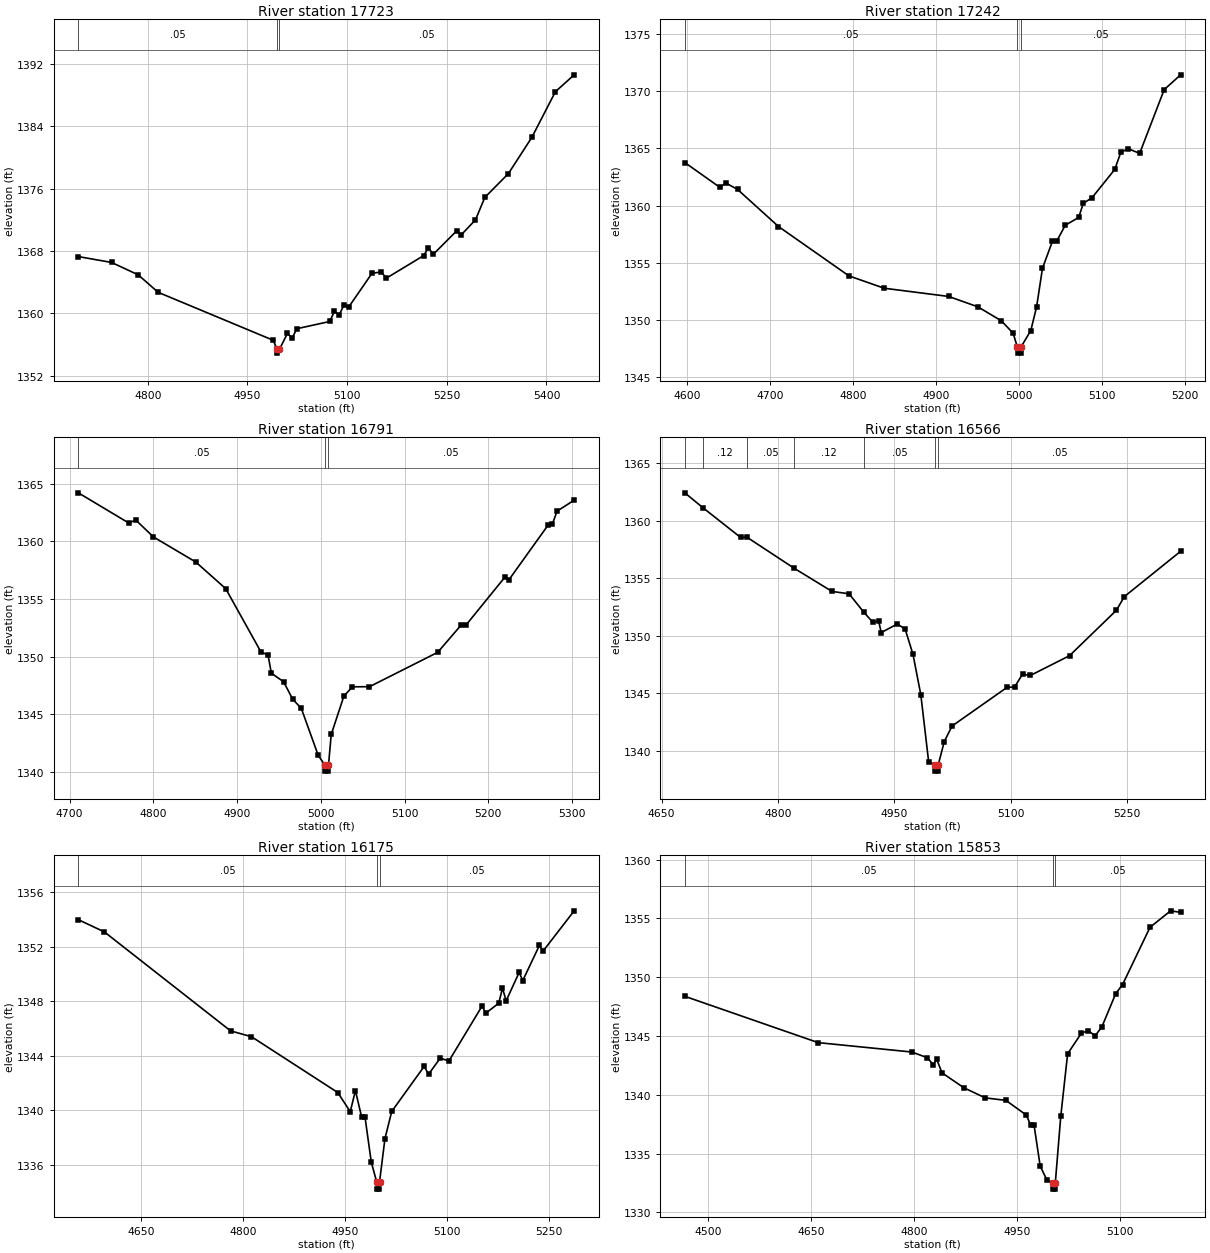
Type RM Length L Ch R = 1,17723,481,481,481
BEGIN DESCRIPTION:
COTTONWOOD CREEK 02 38.0
END DESCRIPTION:
XS GIS Cut Line= 3
      2786705.69     10185353.08      2786716.11     10185125.33
      2786355.70     10184753.12
#Sta/Elev= 30
  4695.6 1367.28  4745.6 1366.53  4785.7 1364.94  4815.7 1362.70  4989.1 1356.54
  4994.3 1355.40  4994.5 1354.90  4998.3 1355.40  5010.2 1357.42  5017.4 1356.85
  5024.4 1358.03  5074.0 1358.96  5081.0 1360.28  5088.1 1359.80  5095.1 1361.02
  5102.3 1360.79  5137.5 1365.14  5151.7 1365.31  5158.9 1364.50  5215.5 1367.42
  5222.4 1368.43  5229.6 1367.56  5264.9 1370.58  5272.1 1370.10  5293.2 1371.99
  5307.3 1374.87  5342.8 1377.93  5378.1 1382.58  5413.5 1388.43  5441.7 1390.59
#Mann=3,-1,0
  4695.6    0.05       0  4994.3    0.03       0  4998.3    0.05       0
Bank Sta=4994.3,4998.3
Exp/Cntr=0.3,0.1

Type RM Length L Ch R = 1,17242,451,451,451
BEGIN DESCRIPTION:
COTTONWOOD CREEK 02 37.0
END DESCRIPTION:
XS GIS Cut Line= 3
      2787205.67     10184953.09      2786883.49     10184641.26
      2786752.46     10184569.01
#Sta/Elev= 30
  4597.1 1363.76  4639.4 1361.59  4646.6 1361.97  4660.7 1361.41  4710.1 1358.17
  4795.0 1353.86  4837.5 1352.78  4915.4 1352.06  4950.7 1351.15  4978.9 1349.93
  4993.1 1348.85  4998.3 1347.61  4998.5 1347.11  5002.0 1347.11  5002.3 1347.61
  5014.4 1349.08  5021.4 1351.15  5028.5 1354.53  5040.5 1356.88  5045.5 1356.88
  5056.0 1358.28  5072.1 1358.96  5077.8 1360.20  5088.2 1360.68  5115.7 1363.16
  5122.9 1364.64  5131.7 1364.97  5145.7 1364.56  5175.3 1370.13  5195.1 1371.42
#Mann=3,-1,0
  4597.1    0.05       0  4998.3    0.05       0  5002.3    0.05       0
Bank Sta=4998.3,5002.3
Exp/Cntr=0.3,0.1

Type RM Length L Ch R = 1,16791,225,225,225
BEGIN DESCRIPTION:
COTTONWOOD CREEK 02 36.0
END DESCRIPTION:
XS GIS Cut Line= 3
      2787392.50     10184710.89      2787260.57     10184521.70
      2786905.68     10184453.11
#Sta/Elev= 30
  4710.4 1364.21  4770.4 1361.60  4779.1 1361.84  4800.1 1360.38  4850.7 1358.20
  4886.4 1355.89  4928.3 1350.42  4937.0 1350.11  4940.9 1348.55  4955.5 1347.81
  4966.4 1346.29  4976.6 1345.51  4996.9 1341.41  5005.1 1340.55  5005.4 1340.05
  5008.9 1340.05  5009.1 1340.55  5012.4 1343.23  5027.5 1346.56  5037.7 1347.37
  5058.1 1347.38  5139.5 1350.36  5167.9 1352.76  5173.0 1352.70  5219.7 1356.88
  5224.8 1356.68  5271.5 1361.42  5276.6 1361.52  5282.1 1362.62  5302.5 1363.57
#Mann=3,-1,0
  4710.4    0.05       0  5005.1    0.05       0  5009.1    0.05       0
Bank Sta=5005.1,5009.1
Exp/Cntr=0.3,0.1

Type RM Length L Ch R = 1,16566,391,391,391
BEGIN DESCRIPTION:
COTTONWOOD CREEK 02 35.0
END DESCRIPTION:
XS GIS Cut Line= 3
      2787559.13     10184427.19      2787334.76     10184306.75
      2786953.73     10184255.62
#Sta/Elev= 30
  4680.0 1362.42  4703.1 1361.14  4752.0 1358.54  4760.2 1358.56  4820.9 1355.87
  4869.8 1353.85  4891.7 1353.65  4910.7 1352.05  4922.3 1351.18  4929.9 1351.28
  4933.2 1350.28  4953.9 1351.02  4964.0 1350.59  4974.1 1348.39  4984.2 1344.89
  4994.3 1339.06  5002.5 1338.74  5002.8 1338.24  5006.3 1338.24  5006.5 1338.74
  5014.4 1340.80  5024.5 1342.16  5095.2 1345.51  5105.2 1345.56  5115.3 1346.66
  5125.4 1346.55  5175.9 1348.27  5236.4 1352.22  5246.5 1353.40  5319.1 1357.34
#Mann=7,-1,0
  4680.0    0.05       0  4703.1    0.12       0  4760.2    0.05       0
  4820.9    0.12       0  4910.7    0.05       0  5002.5    0.05       0
  5006.5    0.05       0
Bank Sta=5002.5,5006.5
Exp/Cntr=0.3,0.1

Type RM Length L Ch R = 1,16175,322,322,322
BEGIN DESCRIPTION:
Mapping XS 45a7f771
END DESCRIPTION:
XS GIS Cut Line= 5
      2787623.42     10184027.99      2787281.98     10183947.16
      2787219.30     10183925.72      2787125.27     10183929.02
      2786922.38     10183849.84
#Sta/Elev= 30
  4557.8 1354.00  4596.1 1353.10  4781.6 1345.83  4812.4 1345.40  4939.2 1341.30
  4957.6 1339.89  4965.2 1341.44  4974.2 1339.53  4979.2 1339.53  4988.5 1336.19
  4996.6 1334.70  4996.8 1334.20  5000.3 1334.20  5000.6 1334.70  5008.6 1337.91
  5018.6 1339.91  5066.3 1343.22  5072.7 1342.64  5090.0 1343.83  5102.6 1343.61
  5151.5 1347.66  5156.9 1347.13  5175.9 1347.86  5181.4 1348.97  5186.8 1348.04
  5205.9 1350.12  5211.3 1349.53  5235.7 1352.11  5241.1 1351.69  5286.8 1354.65
#Mann=3,-1,0
  4557.8    0.05       0  4996.6    0.05       0  5000.6    0.05       0
Bank Sta=4996.6,5000.6
Exp/Cntr=0.3,0.1

Type RM Length L Ch R = 1,15853,397,397,397
BEGIN DESCRIPTION:
COTTONWOOD CREEK 02 34.0
END DESCRIPTION:
XS GIS Cut Line= 3
      2787588.79     10183770.67      2787185.24     10183626.70
      2786891.05     10183632.11
#Sta/Elev= 30
  4465.6 1348.37  4660.0 1344.43  4796.7 1343.63  4819.3 1343.14  4827.5 1342.56
  4832.8 1343.01  4840.5 1341.86  4872.4 1340.59  4903.6 1339.73  4933.6 1339.52
  4963.6 1338.26  4969.7 1337.40  4974.7 1337.40  4983.6 1333.93  4993.6 1332.72
  5001.6 1332.47  5001.9 1331.97  5005.4 1331.97  5005.6 1332.47  5013.6 1338.17
  5023.6 1343.48  5043.6 1345.23  5053.6 1345.46  5063.6 1345.00  5073.6 1345.78
  5093.7 1348.60  5103.7 1349.37  5143.7 1354.24  5173.7 1355.64  5188.3 1355.51
#Mann=3,-1,0
  4465.6    0.05       0  5001.6    0.05       0  5005.6    0.05       0
Bank Sta=5001.6,5005.6
Exp/Cntr=0.3,0.1

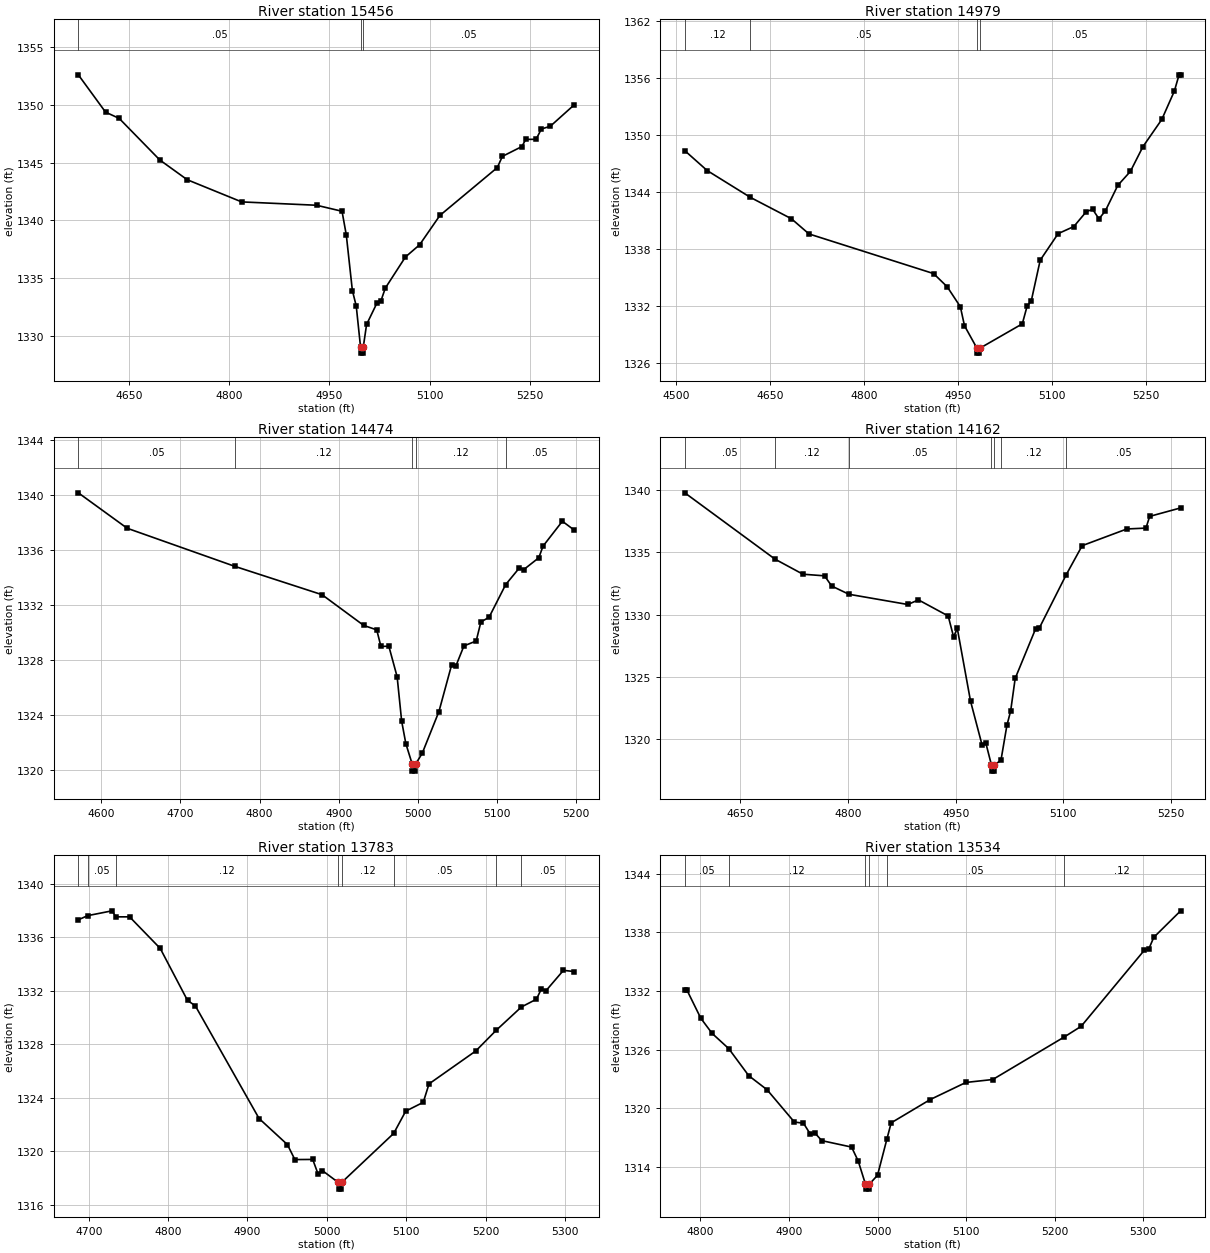
Type RM Length L Ch R = 1,15456,477,477,477
BEGIN DESCRIPTION:
COTTONWOOD CREEK 02 33.0
END DESCRIPTION:
XS GIS Cut Line= 3
      2787755.72     10183453.12      2787390.84     10183379.73
      2787073.66     10183187.45
#Sta/Elev= 30
  4573.6 1352.59  4614.4 1349.36  4634.8 1348.82  4695.7 1345.22  4736.8 1343.51
  4818.4 1341.59  4930.6 1341.30  4968.8 1340.78  4975.2 1338.73  4984.3 1333.92
  4990.1 1332.58  4996.6 1329.00  4996.8 1328.50  5000.3 1328.50  5000.6 1329.00
  5005.6 1330.98  5021.1 1332.83  5026.9 1332.99  5033.7 1334.13  5063.8 1336.82
  5085.1 1337.88  5115.5 1340.42  5201.5 1344.56  5209.1 1345.53  5238.3 1346.38
  5244.2 1347.00  5259.6 1347.01  5267.6 1347.90  5281.0 1348.14  5316.7 1349.99
#Mann=3,-1,0
  4573.6    0.05       0  4996.6    0.05       0  5000.6    0.05       0
Bank Sta=4996.6,5000.6
Exp/Cntr=0.3,0.1

Type RM Length L Ch R = 1,14979,505,505,505
BEGIN DESCRIPTION:
COTTONWOOD CREEK 02 32.0
END DESCRIPTION:
XS GIS Cut Line= 3
      2787855.68     10183303.10      2787470.02     10182846.94
      2787455.68     10182653.11
#Sta/Elev= 30
  4514.0 1348.33  4549.7 1346.24  4618.9 1343.41  4684.2 1341.17  4712.3 1339.57
  4911.2 1335.40  4933.0 1334.01  4954.0 1331.91  4960.6 1329.91  4980.6 1327.53
  4980.8 1327.03  4984.4 1327.03  4984.7 1327.53  5052.9 1330.11  5060.6 1331.98
  5067.2 1332.52  5081.5 1336.81  5110.1 1339.60  5135.2 1340.35  5155.3 1341.93
  5165.3 1342.15  5175.3 1341.16  5185.4 1341.98  5205.4 1344.68  5225.5 1346.15
  5245.5 1348.75  5275.6 1351.61  5295.7 1354.60  5303.2 1356.31  5305.7 1356.31
#Mann=4,-1,0
  4514.0    0.12       0  4618.9    0.05       0  4980.6    0.03       0
  4984.7    0.05       0
Bank Sta=4980.6,4984.7
Exp/Cntr=0.3,0.1

Type RM Length L Ch R = 1,14474,312,312,312
BEGIN DESCRIPTION:
COTTONWOOD CREEK 02 31.0
END DESCRIPTION:
XS GIS Cut Line= 3
      2788030.85     10183025.09      2787870.85     10182548.38
      2787755.67     10182503.11
#Sta/Elev= 30
  4570.9 1340.17  4632.6 1337.59  4768.9 1334.81  4878.9 1332.75  4931.6 1330.51
  4948.0 1330.19  4953.3 1328.98  4963.3 1329.00  4973.8 1326.77  4979.5 1323.54
  4984.8 1321.90  4992.9 1320.40  4993.1 1319.90  4996.7 1319.90  4997.0 1320.40
  5005.5 1321.20  5026.6 1324.24  5042.6 1327.63  5047.9 1327.54  5058.2 1329.02
  5073.7 1329.38  5079.6 1330.76  5090.0 1331.11  5111.0 1333.49  5128.4 1334.71
  5133.8 1334.58  5152.8 1335.44  5158.2 1336.29  5182.6 1338.10  5197.5 1337.46
#Mann=5,-1,0
  4570.9    0.05       0  4768.9    0.12       0  4992.9    0.07       0
  4997.0    0.12       0  5111.0    0.05       0
Bank Sta=4992.9,4997
Exp/Cntr=0.3,0.1

Type RM Length L Ch R = 1,14162,379,379,379
BEGIN DESCRIPTION:
COTTONWOOD CREEK 02 30.0
END DESCRIPTION:
XS GIS Cut Line= 3
      2788250.24     10182987.20      2788227.85     10182676.67
      2788128.17     10182310.84
#Sta/Elev= 30
  4572.7 1339.77  4698.3 1334.45  4737.2 1333.24  4767.3 1333.11  4777.3 1332.29
  4801.3 1331.63  4883.3 1330.81  4898.1 1331.18  4939.5 1329.89  4947.0 1328.22
  4952.2 1328.89  4970.6 1323.06  4986.8 1319.51  4992.0 1319.68  4999.7 1317.94
  4999.9 1317.44  5003.5 1317.44  5003.8 1317.94  5013.0 1318.31  5021.3 1321.12
  5026.5 1322.27  5032.8 1324.88  5061.1 1328.84  5066.3 1328.91  5103.8 1333.19
  5126.1 1335.53  5188.3 1336.87  5214.9 1336.94  5220.1 1337.88  5263.2 1338.56
#Mann=7,-1,0
  4572.7    0.05       0  4698.3    0.12       0  4801.3    0.05       0
  4999.7    0.05       0  5003.8    0.05       0  5013.0    0.12       0
  5103.8    0.05       0
Bank Sta=4999.7,5003.8
Exp/Cntr=0.3,0.1

Type RM Length L Ch R = 1,13783,249,249,249
BEGIN DESCRIPTION:
Mapping XS 1ad8a321
END DESCRIPTION:
XS GIS Cut Line= 2
      2788690.67     10182705.13      2788402.01     10182150.90
#Sta/Elev= 30
  4686.8 1337.30  4698.6 1337.61  4729.3 1337.97  4734.1 1337.52  4751.4 1337.52
  4790.0 1335.16  4824.4 1331.27  4834.2 1330.87  4914.6 1322.44  4950.3 1320.49
  4959.7 1319.37  4982.2 1319.38  4988.9 1318.30  4994.5 1318.54  5014.4 1317.66
  5014.7 1317.16  5018.4 1317.16  5018.7 1317.66  5084.3 1321.33  5099.4 1322.99
  5121.5 1323.65  5128.8 1325.03  5187.7 1327.49  5213.5 1329.04  5245.2 1330.78
  5264.1 1331.36  5270.5 1332.14  5276.1 1331.99  5298.2 1333.52  5311.7 1333.43
#Mann=8,-1,0
  4686.8    0.12       0  4698.6    0.05       0  4734.1    0.12       0
  5014.4    0.07       0  5018.7    0.12       0  5084.3    0.05       0
  5213.5    0.12       0  5245.2    0.05       0
Bank Sta=5014.4,5018.7
Exp/Cntr=0.3,0.1

Type RM Length L Ch R = 1,13534,241,241,241
BEGIN DESCRIPTION:
COTTONWOOD CREEK 02 29.0
END DESCRIPTION:
XS GIS Cut Line= 3
      2788805.69     10182503.13      2788753.00     10182292.00
      2788705.68     10181953.09
#Sta/Elev= 30
  4782.4 1332.06  4785.0 1332.06  4800.5 1329.21  4813.3 1327.66  4832.0 1326.11
  4854.6 1323.34  4875.2 1321.91  4906.1 1318.60  4916.4 1318.48  4924.3 1317.34
  4929.4 1317.47  4937.0 1316.70  4970.7 1316.04  4978.2 1314.61  4986.4 1312.24
  4986.7 1311.74  4990.4 1311.74  4990.7 1312.24  5000.0 1313.16  5010.7 1316.90
  5015.4 1318.52  5059.5 1320.90  5099.8 1322.65  5130.1 1322.95  5210.3 1327.27
  5229.9 1328.39  5301.4 1336.19  5306.4 1336.33  5311.9 1337.49  5342.2 1340.20
#Mann=6,-1,0
  4782.4    0.05       0  4832.0    0.12       0  4986.4    0.07       0
  4990.7    0.12       0  5010.7    0.05       0  5210.3    0.12       0
Bank Sta=4986.4,4990.7
Exp/Cntr=0.3,0.1

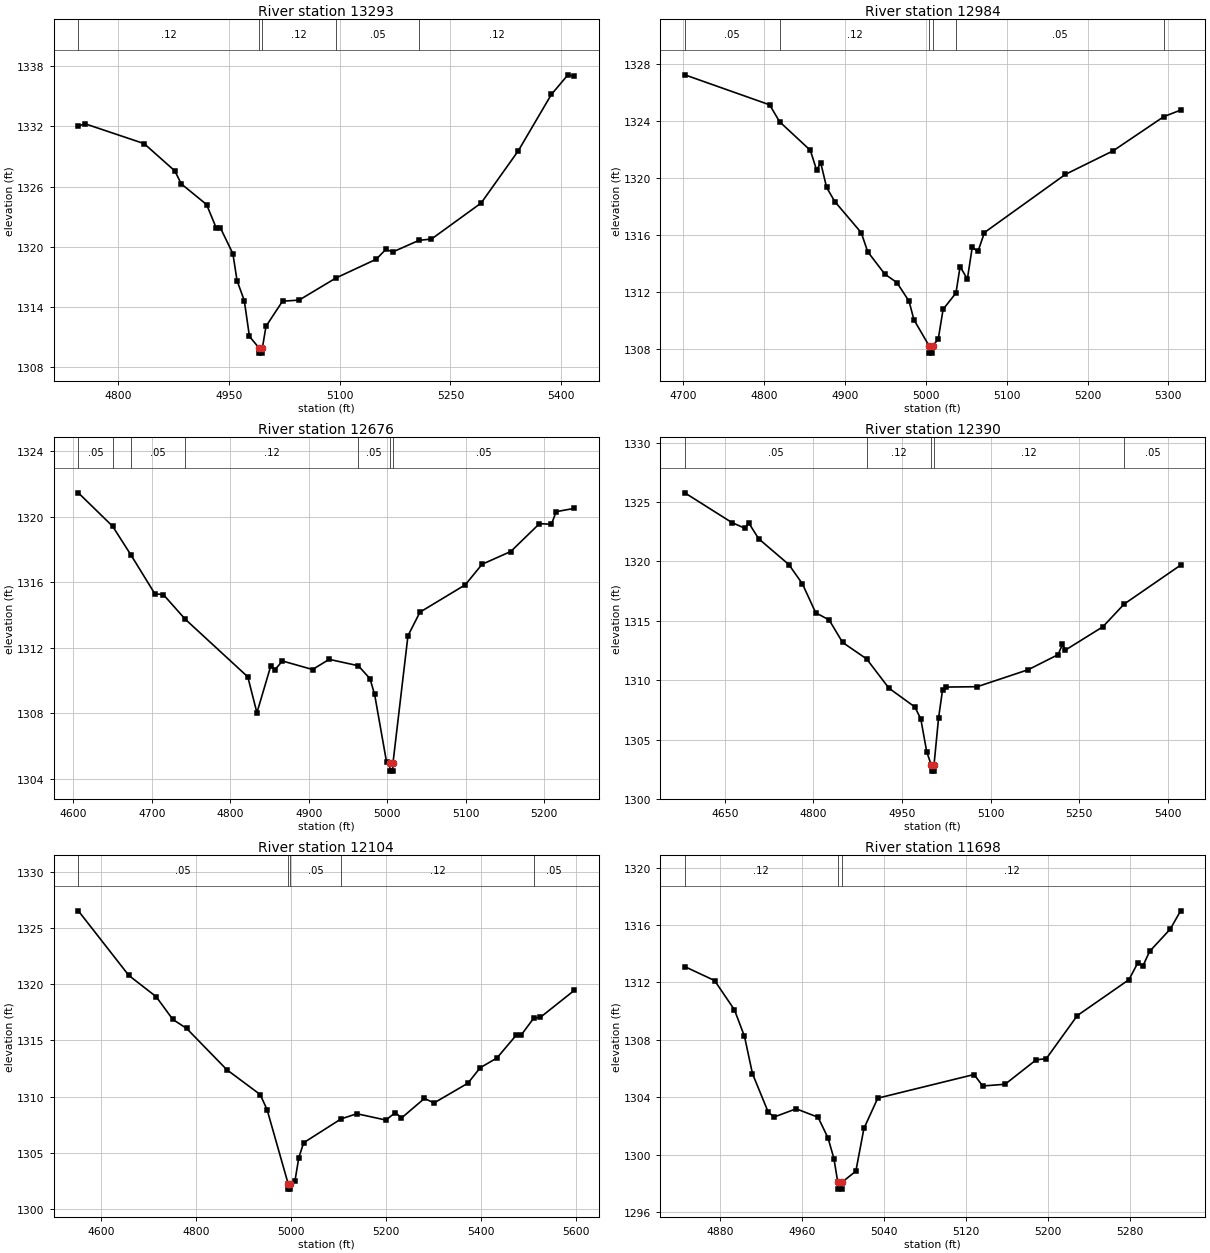
Type RM Length L Ch R = 1,13293,309,309,309
BEGIN DESCRIPTION:
COTTONWOOD CREEK 02 28.0
END DESCRIPTION:
XS GIS Cut Line= 3
      2789040.35     10182521.98      2789027.15     10182348.79
      2788805.67     10181903.08
#Sta/Elev= 30
  4746.1 1332.02  4755.0 1332.25  4835.2 1330.27  4876.8 1327.55  4885.4 1326.27
  4919.8 1324.20  4933.0 1321.84  4938.6 1321.86  4955.4 1319.31  4961.0 1316.63
  4970.8 1314.65  4977.8 1311.07  4991.0 1309.91  4991.3 1309.41  4995.0 1309.41
  4995.3 1309.91  5000.2 1312.08  5022.6 1314.58  5045.0 1314.69  5095.2 1316.90
  5149.5 1318.76  5162.6 1319.75  5171.8 1319.48  5207.4 1320.64  5224.3 1320.77
  5291.5 1324.35  5341.8 1329.55  5386.7 1335.17  5409.1 1337.12  5417.5 1336.97
#Mann=5,-1,0
  4746.1    0.12       0  4991.0    0.07       0  4995.3    0.12       0
  5095.2    0.05       0  5207.4    0.12       0
Bank Sta=4991,4995.3
Exp/Cntr=0.3,0.1

Type RM Length L Ch R = 1,12984,308,308,308
BEGIN DESCRIPTION:
Mapping XS a9c1b534
END DESCRIPTION:
XS GIS Cut Line= 3
      2789221.80     10182327.30      2789244.88     10182126.11
      2789017.24     10181784.65
#Sta/Elev= 30
  4702.2 1327.25  4807.1 1325.14  4819.4 1323.95  4857.4 1321.94  4865.2 1320.54
  4870.2 1321.07  4877.5 1319.33  4887.6 1318.34  4920.3 1316.15  4928.3 1314.81
  4949.4 1313.24  4964.4 1312.64  4979.4 1311.33  4985.4 1310.03  5004.3 1308.18
  5004.6 1307.68  5008.3 1307.68  5008.6 1308.18  5015.5 1308.67  5021.5 1310.76
  5037.4 1311.91  5042.5 1313.76  5051.5 1312.89  5057.5 1315.12  5064.6 1314.83
  5072.6 1316.16  5172.7 1320.25  5231.8 1321.91  5294.3 1324.31  5315.1 1324.77
#Mann=6,-1,0
  4702.2    0.05       0  4819.4    0.12       0  5004.3    0.07       0
  5008.6    0.12       0  5037.4    0.05       0  5294.3    0.12       0
Bank Sta=5004.3,5008.6
Exp/Cntr=0.3,0.1

Type RM Length L Ch R = 1,12676,286,286,286
BEGIN DESCRIPTION:
COTTONWOOD CREEK 02 27.0
END DESCRIPTION:
XS GIS Cut Line= 3
      2789755.69     10182053.12      2789484.06     10181939.72
      2789305.70     10181653.14
#Sta/Elev= 30
  4606.4 1321.46  4650.1 1319.42  4673.7 1317.65  4703.9 1315.30  4714.8 1315.25
  4742.4 1313.76  4822.4 1310.23  4834.0 1308.04  4851.6 1310.89  4857.0 1310.67
  4866.5 1311.20  4904.9 1310.68  4926.1 1311.30  4963.2 1310.91  4978.1 1310.12
  4984.0 1309.16  4999.3 1305.01  5003.1 1304.98  5003.4 1304.48  5007.1 1304.48
  5007.4 1304.98  5026.5 1312.74  5041.8 1314.18  5099.6 1315.85  5120.9 1317.10
  5157.5 1317.88  5194.1 1319.58  5209.4 1319.54  5215.3 1320.31  5238.3 1320.51
#Mann=7,-1,0
  4606.4    0.05       0  4650.1    0.12       0  4673.7    0.05       0
  4742.4    0.12       0  4963.2    0.05       0  5003.1    0.05       0
  5007.4    0.05       0
Bank Sta=5003.1,5007.4
Exp/Cntr=0.3,0.1

Type RM Length L Ch R = 1,12390,286,286,286
BEGIN DESCRIPTION:
Mapping XS 19772522
END DESCRIPTION:
XS GIS Cut Line= 4
      2789855.22     10182159.13      2789706.75     10181845.70
      2789698.50     10181721.98      2789348.92     10181605.46
#Sta/Elev= 30
  4582.2 1325.78  4661.8 1323.28  4684.6 1322.78  4690.1 1323.27  4707.3 1321.91
  4758.3 1319.74  4781.1 1318.13  4803.8 1315.68  4826.6 1315.07  4849.3 1313.18
  4890.0 1311.79  4927.7 1309.33  4971.7 1307.74  4981.7 1306.73  4991.7 1303.97
  4999.5 1302.84  4999.9 1302.34  5003.7 1302.34  5004.0 1302.84  5011.8 1306.83
  5018.5 1309.18  5023.5 1309.42  5077.1 1309.45  5163.4 1310.88  5214.1 1312.15
  5221.4 1313.01  5226.6 1312.54  5289.9 1314.50  5325.9 1316.41  5421.5 1319.69
#Mann=5,-1,0
  4582.2    0.05       0  4890.0    0.12       0  4999.5    0.07       0
  5004.0    0.12       0  5325.9    0.05       0
Bank Sta=4999.5,5004
Exp/Cntr=0.3,0.1

Type RM Length L Ch R = 1,12104,406,406,406
BEGIN DESCRIPTION:
COTTONWOOD CREEK 02 26.0
END DESCRIPTION:
XS GIS Cut Line= 3
      2790255.65     10181953.07      2790028.53     10181674.66
      2789355.73     10181553.12
#Sta/Elev= 30
  4552.4 1326.53  4658.6 1320.78  4716.1 1318.89  4751.2 1316.86  4780.0 1316.07
  4864.7 1312.39  4934.9 1310.18  4949.4 1308.84  4993.6 1302.26  4993.9 1301.76
  4997.8 1301.76  4998.1 1302.26  5008.0 1302.47  5016.2 1304.56  5026.4 1305.89
  5105.1 1308.01  5138.2 1308.47  5199.1 1307.91  5219.5 1308.57  5232.2 1308.09
  5280.4 1309.83  5300.7 1309.43  5371.9 1311.19  5397.9 1312.57  5432.9 1313.43
  5473.5 1315.46  5483.7 1315.46  5510.4 1316.98  5524.3 1317.05  5595.4 1319.44
#Mann=5,-1,0
  4552.4    0.05       0  4993.6    0.05       0  4998.1    0.05       0
  5105.1    0.12       0  5510.4    0.05       0
Bank Sta=4993.6,4998.1
Exp/Cntr=0.3,0.1

Type RM Length L Ch R = 1,11698,289,289,289
BEGIN DESCRIPTION:
COTTONWOOD CREEK 02 25.0
END DESCRIPTION:
XS GIS Cut Line= 3
      2789955.68     10181253.12      2789762.83     10181368.99
      2789505.67     10181403.11
#Sta/Elev= 30
  4845.2 1313.10  4874.3 1312.13  4893.7 1310.09  4903.5 1308.24  4911.3 1305.64
  4926.8 1302.94  4932.6 1302.62  4954.0 1303.19  4975.4 1302.60  4985.1 1301.16
  4990.9 1299.72  4994.6 1298.09  4994.9 1297.59  4998.8 1297.59  4999.1 1298.09
  5012.3 1298.84  5020.2 1301.82  5033.7 1303.93  5127.8 1305.58  5136.2 1304.78
  5158.1 1304.90  5188.4 1306.60  5198.4 1306.69  5228.7 1309.69  5279.1 1312.19
  5287.9 1313.38  5292.9 1313.17  5299.3 1314.16  5319.5 1315.72  5329.6 1316.99
#Mann=3,-1,0
  4845.2    0.12       0  4994.6    0.07       0  4999.1    0.12       0
Bank Sta=4994.6,4999.1
Exp/Cntr=0.3,0.1

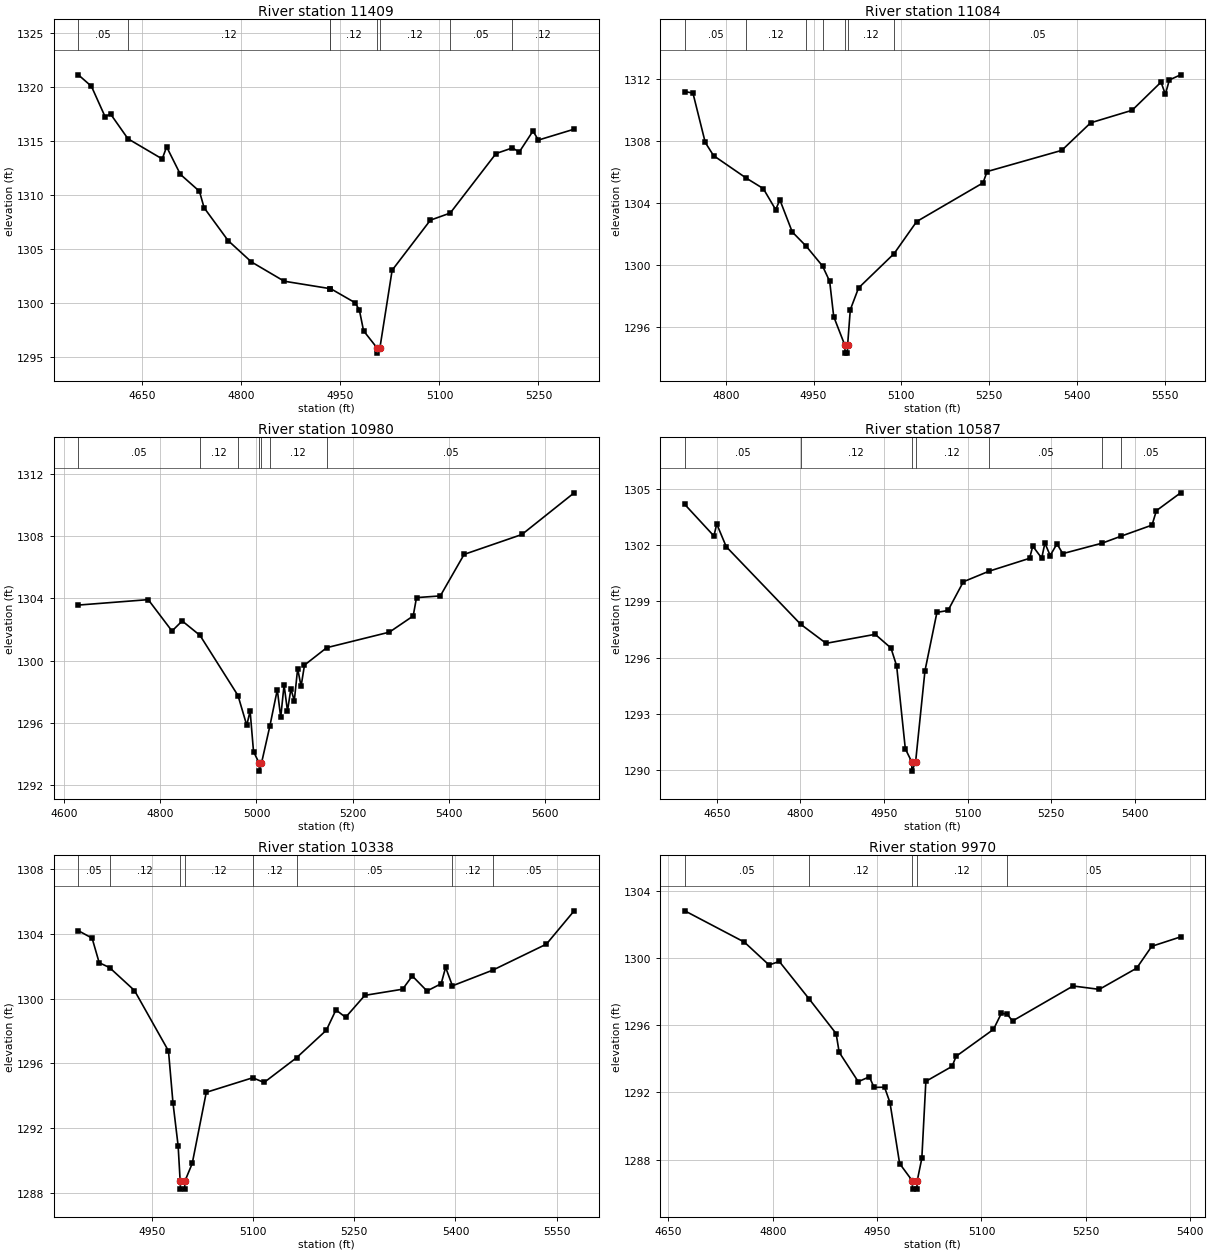
Type RM Length L Ch R = 1,11409,325,325,325
BEGIN DESCRIPTION:
Mapping XS 6a67d7c9
END DESCRIPTION:
XS GIS Cut Line= 2
      2789955.80     10180905.50      2789364.18     10181368.57
#Sta/Elev= 30
  4552.8 1321.15  4572.6 1320.09  4593.4 1317.26  4601.6 1317.52  4628.0 1315.22
  4679.9 1313.35  4686.6 1314.47  4707.4 1311.92  4736.3 1310.35  4743.4 1308.82
  4779.7 1305.78  4815.0 1303.80  4864.7 1302.01  4934.3 1301.32  4934.8 1301.33
  4972.0 1300.02  4978.6 1299.35  4985.0 1297.41  5005.2 1295.84  5005.6 1295.34
  5009.8 1295.84  5028.3 1303.03  5086.2 1307.67  5116.3 1308.33  5185.7 1313.85
  5210.5 1314.37  5220.9 1313.99  5241.7 1315.94  5249.9 1315.10  5304.1 1316.11
#Mann=8,-1,0
  4552.8    0.05       0  4628.0    0.12       0  4934.3    0.05       0
  4934.8    0.12       0  5005.2    0.07       0  5009.8    0.12       0
  5116.3    0.05       0  5210.5    0.12       0
Bank Sta=5005.2,5009.8
Exp/Cntr=0.3,0.1

Type RM Length L Ch R = 1,11084,104,104,104
BEGIN DESCRIPTION:
COTTONWOOD CREEK 02 24.0
END DESCRIPTION:
XS GIS Cut Line= 3
      2789713.31     10180671.28      2789456.02     10180941.77
      2789110.17     10181264.57
#Sta/Elev= 30
  4730.2 1311.19  4744.1 1311.09  4765.1 1307.90  4779.3 1307.05  4835.0 1305.60
  4864.2 1304.92  4885.3 1303.56  4892.5 1304.19  4913.6 1302.12  4937.4 1301.20
  4965.3 1299.92  4977.5 1298.93  4984.4 1296.65  5003.5 1294.79  5003.8 1294.29
  5007.7 1294.29  5008.1 1294.79  5012.7 1297.09  5026.8 1298.50  5087.5 1300.72
  5126.0 1302.79  5239.3 1305.29  5246.2 1306.02  5373.7 1307.39  5423.0 1309.17
  5493.8 1309.98  5543.2 1311.80  5550.5 1311.01  5557.4 1311.94  5576.6 1312.27
#Mann=7,-1,0
  4730.2    0.05       0  4835.0    0.12       0  4937.4    0.05       0
  4965.3    0.12       0  5003.5    0.07       0  5008.1    0.12       0
  5087.5    0.05       0
Bank Sta=5003.5,5008.1
Exp/Cntr=0.3,0.1

Type RM Length L Ch R = 1,10980,393,393,393
BEGIN DESCRIPTION:
COTTONWOOD CREEK 02 23.0
END DESCRIPTION:
XS GIS Cut Line= 3
      2789756.26     10180507.93      2789352.10     10180908.78
      2789020.64     10181232.00
#Sta/Elev= 30
  4629.2 1303.57  4774.7 1303.92  4824.2 1301.90  4845.4 1302.55  4882.5 1301.62
  4961.6 1297.75  4979.8 1295.84  4986.8 1296.76  4993.9 1294.15  5005.8 1293.39
  5006.1 1292.89  5010.4 1293.39  5027.8 1295.77  5043.4 1298.13  5050.5 1296.35
  5057.5 1298.43  5064.6 1296.76  5071.7 1298.18  5078.8 1297.42  5085.8 1299.49
  5092.9 1298.34  5100.0 1299.71  5146.3 1300.83  5276.8 1301.83  5326.3 1302.87
  5333.2 1304.05  5382.8 1304.16  5432.3 1306.83  5552.6 1308.11  5661.4 1310.79
#Mann=7,-1,0
  4629.2    0.05       0  4882.5    0.12       0  4961.6    0.05       0
  5005.8    0.05       0  5010.4    0.05       0  5027.8    0.12       0
  5146.3    0.05       0
Bank Sta=5005.8,5010.4
Exp/Cntr=0.3,0.1

Type RM Length L Ch R = 1,10587,249,249,249
BEGIN DESCRIPTION:
Mapping XS cb8d4547
END DESCRIPTION:
XS GIS Cut Line= 4
      2789789.20     10180489.81      2789451.07     10180540.94
      2789427.98     10180422.18      2789220.68     10180048.14
#Sta/Elev= 30
  4592.2 1304.16  4644.5 1302.48  4649.6 1303.12  4666.6 1301.91  4800.2 1297.78
  4846.0 1296.76  4934.2 1297.24  4962.5 1296.51  4972.7 1295.56  4988.3 1291.14
  4999.7 1290.45  5000.2 1289.95  5006.8 1290.45  5023.6 1295.30  5045.1 1298.41
  5065.0 1298.51  5092.5 1300.04  5138.3 1300.60  5211.5 1301.29  5217.2 1301.94
  5233.3 1301.30  5239.0 1302.10  5248.5 1301.44  5260.7 1302.06  5271.1 1301.54
  5342.0 1302.10  5375.9 1302.47  5431.4 1303.06  5439.3 1303.83  5482.8 1304.78
#Mann=7,-1,0
  4592.2    0.05       0  4800.2    0.12       0  4999.7    0.07       0
  5006.8    0.12       0  5138.3    0.05       0  5342.0    0.12       0
  5375.9    0.05       0
Bank Sta=4999.7,5006.8
Exp/Cntr=0.3,0.1

Type RM Length L Ch R = 1,10338,368,368,368
BEGIN DESCRIPTION:
COTTONWOOD CREEK 02 22.0
END DESCRIPTION:
XS GIS Cut Line= 3
      2789805.66     10180453.11      2789731.49     10180438.67
      2789229.63     10180011.20
#Sta/Elev= 30
  4841.1 1304.21  4861.5 1303.75  4872.0 1302.23  4887.3 1301.93  4924.3 1300.51
  4974.7 1296.77  4981.3 1293.58  4989.0 1290.90  4992.0 1288.72  4992.5 1288.22
  4998.6 1288.22  4999.1 1288.72  5009.9 1289.81  5030.7 1294.21  5099.5 1295.11
  5116.4 1294.82  5164.5 1296.35  5208.6 1298.05  5222.9 1299.31  5237.2 1298.85
  5265.7 1300.21  5321.7 1300.59  5336.0 1301.41  5357.8 1300.48  5378.8 1300.93
  5385.4 1301.94  5395.5 1300.80  5455.3 1301.77  5534.8 1303.38  5575.9 1305.44
#Mann=8,-1,0
  4841.1    0.05       0  4887.3    0.12       0  4992.0    0.05       0
  4999.1    0.12       0  5099.5    0.12       0  5164.5    0.05       0
  5395.5    0.12       0  5455.3    0.05       0
Bank Sta=4992,4999.1
Exp/Cntr=0.3,0.1

Type RM Length L Ch R = 1,9970,482,482,482
BEGIN DESCRIPTION:
COTTONWOOD CREEK 02 21.0
END DESCRIPTION:
XS GIS Cut Line= 3
      2790058.79     10180239.43      2789883.29     10180110.87
      2789450.64     10179870.06
#Sta/Elev= 30
  4673.6 1302.80  4759.2 1300.94  4794.7 1299.58  4809.4 1299.79  4852.7 1297.54
  4891.1 1295.50  4895.5 1294.39  4922.9 1292.64  4938.9 1292.93  4945.6 1292.30
  4960.7 1292.31  4968.5 1291.40  4982.4 1287.77  5000.5 1286.75  5001.0 1286.25
  5007.2 1286.25  5007.7 1286.75  5014.3 1288.08  5020.1 1292.66  5057.8 1293.55
  5063.6 1294.15  5117.3 1295.75  5128.7 1296.71  5137.0 1296.65  5144.7 1296.25
  5231.7 1298.33  5269.4 1298.13  5323.1 1299.39  5344.8 1300.69  5386.3 1301.25
#Mann=5,-1,0
  4673.6    0.05       0  4852.7    0.12       0  5000.5    0.07       0
  5007.7    0.12       0  5137.0    0.05       0
Bank Sta=5000.5,5007.7
Exp/Cntr=0.3,0.1