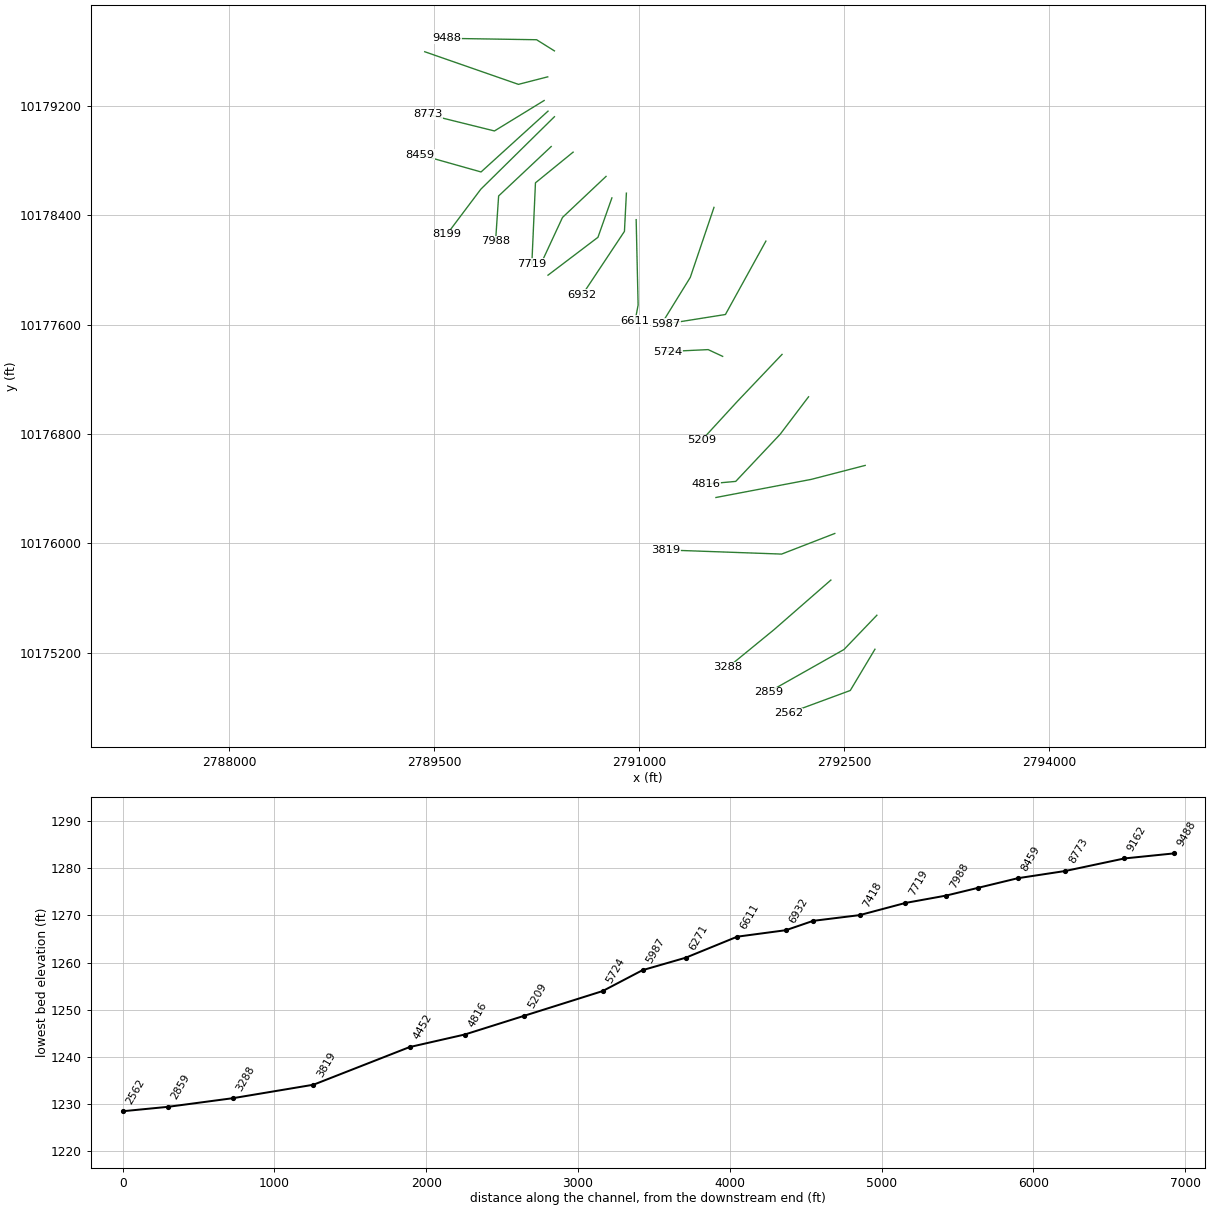
HEC-RAS study COTTONWOOD CREEK 02.prj: COTTONWOOD CREEK 02 Base Level Engineering

--- COTTONWOOD CREEK 02.g01 (geometry) --- (continued)

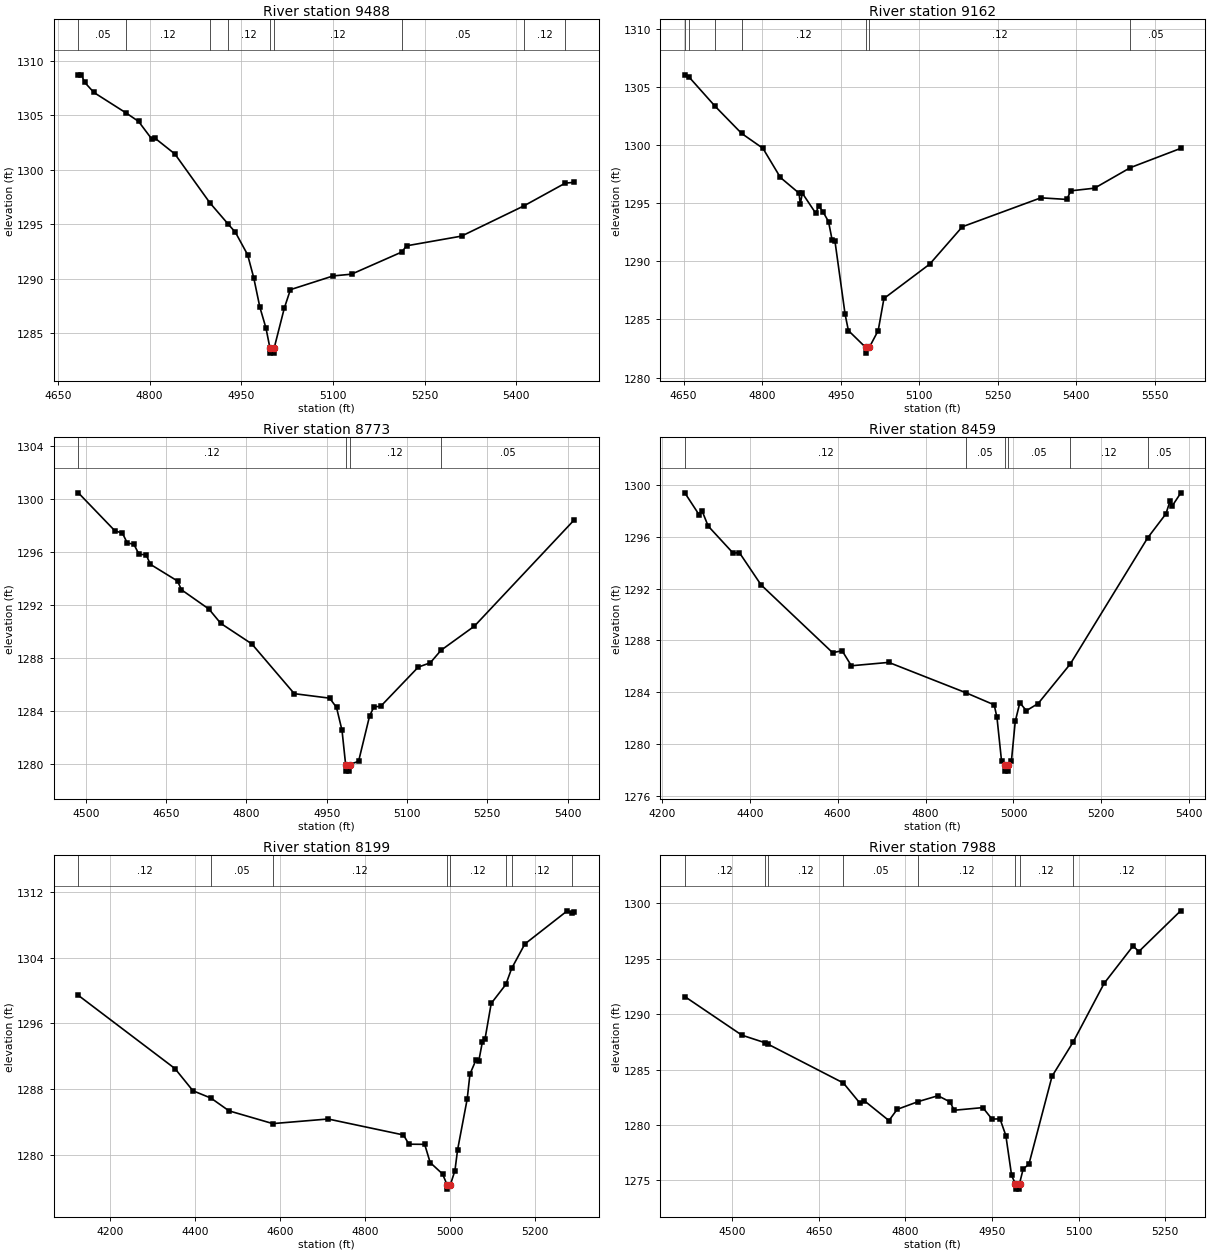
Type RM Length L Ch R = 1,9488,326,326,326
BEGIN DESCRIPTION:
Mapping XS f3b27310
END DESCRIPTION:
XS GIS Cut Line= 3
      2790379.25     10179602.68      2790248.61     10179684.33
      2789591.44     10179694.54
#Sta/Elev= 30
  4683.3 1308.69  4688.4 1308.69  4693.5 1308.01  4708.8 1307.07  4761.8 1305.18
  4781.8 1304.42  4803.1 1302.83  4809.0 1302.87  4841.3 1301.43  4898.7 1296.94
  4928.8 1294.98  4940.3 1294.25  4960.3 1292.19  4970.3 1290.08  4980.3 1287.39
  4990.3 1285.47  4996.7 1283.67  4997.2 1283.17  5003.4 1283.17  5003.9 1283.67
  5020.3 1287.29  5030.3 1288.99  5100.3 1290.25  5130.3 1290.41  5212.5 1292.44
  5220.3 1293.01  5310.3 1293.90  5412.3 1296.67  5480.1 1298.76  5494.6 1298.83
#Mann=9,-1,0
  4683.3    0.05       0  4761.8    0.12       0  4898.7    0.05       0
  4928.8    0.12       0  4996.7    0.07       0  5003.9    0.12       0
  5212.5    0.05       0  5412.3    0.12       0  5480.1    0.05       0
Bank Sta=4996.7,5003.9
Exp/Cntr=0.3,0.1

Type RM Length L Ch R = 1,9162,389,389,389
BEGIN DESCRIPTION:
COTTONWOOD CREEK 02 20.0
END DESCRIPTION:
XS GIS Cut Line= 3
      2790330.22     10179412.89      2790115.95     10179357.80
      2789430.46     10179596.50
#Sta/Elev= 30
  4652.3 1306.04  4660.0 1305.87  4710.1 1303.34  4760.8 1301.00  4801.5 1299.72
  4834.9 1297.21  4870.5 1295.86  4872.9 1294.92  4876.8 1295.86  4902.6 1294.12
  4907.9 1294.78  4916.2 1294.26  4926.8 1293.42  4933.7 1291.84  4939.0 1291.77
  4958.5 1285.44  4964.8 1284.04  4997.6 1282.60  4998.1 1282.10  5004.8 1282.60
  5021.7 1284.04  5032.7 1286.80  5120.2 1289.76  5182.4 1292.97  5332.5 1295.46
  5382.1 1295.32  5389.4 1296.06  5435.0 1296.29  5503.6 1298.06  5599.4 1299.71
#Mann=7,-1,0
  4652.3    0.05       0  4660.0    0.12       0  4710.1    0.05       0
  4760.8    0.12       0  4997.6    0.07       0  5004.8    0.12       0
  5503.6    0.05       0
Bank Sta=4997.6,5004.8
Exp/Cntr=0.3,0.1

Type RM Length L Ch R = 1,8773,314,314,314
BEGIN DESCRIPTION:
COTTONWOOD CREEK 02 19.0
END DESCRIPTION:
XS GIS Cut Line= 3
      2790303.73     10179239.44      2789940.44     10179016.97
      2789454.73     10179137.38
#Sta/Elev= 30
  4485.9 1300.46  4554.0 1297.60  4568.3 1297.41  4577.4 1296.67  4589.6 1296.58
  4599.2 1295.82  4612.6 1295.78  4620.5 1295.06  4671.2 1293.80  4678.5 1293.14
  4729.9 1291.68  4752.0 1290.60  4810.0 1289.05  4889.4 1285.29  4955.5 1284.95
  4968.3 1284.25  4978.6 1282.51  4985.3 1279.94  4985.8 1279.44  4992.1 1279.44
  4992.6 1279.94  5009.5 1280.18  5030.1 1283.61  5038.3 1284.30  5050.7 1284.33
  5121.1 1287.30  5143.4 1287.62  5163.6 1288.57  5225.9 1290.39  5412.3 1298.41
#Mann=4,-1,0
  4485.9    0.12       0  4985.3    0.07       0  4992.6    0.12       0
  5163.6    0.05       0
Bank Sta=4985.3,4992.6
Exp/Cntr=0.3,0.1

Type RM Length L Ch R = 1,8459,260,260,260
BEGIN DESCRIPTION:
Mapping XS a692bcc5
END DESCRIPTION:
XS GIS Cut Line= 3
      2790332.31     10179161.90      2789842.48     10178716.97
      2789393.50     10178843.50
#Sta/Elev= 30
  4252.2 1299.40  4284.5 1297.72  4291.2 1298.03  4305.4 1296.83  4362.2 1294.74
  4376.4 1294.78  4425.7 1292.29  4588.6 1287.05  4610.2 1287.20  4631.2 1286.04
  4716.3 1286.30  4892.2 1283.95  4956.2 1283.02  4962.5 1282.05  4972.9 1278.69
  4979.7 1278.40  4980.2 1277.90  4986.5 1277.90  4987.0 1278.40  4995.4 1278.69
  5004.1 1281.74  5014.5 1283.18  5029.4 1282.57  5056.1 1283.12  5129.4 1286.18
  5305.4 1295.92  5347.0 1297.78  5356.3 1298.77  5361.5 1298.40  5380.4 1299.37
#Mann=6,-1,0
  4252.2    0.12       0  4892.2    0.05       0  4979.7    0.05       0
  4987.0    0.05       0  5129.4    0.12       0  5305.4    0.05       0
Bank Sta=4979.7,4987
Exp/Cntr=0.3,0.1

Type RM Length L Ch R = 1,8199,211,211,211
BEGIN DESCRIPTION:
COTTONWOOD CREEK 02 18.0
END DESCRIPTION:
XS GIS Cut Line= 3
      2790379.25     10179121.09      2789840.43     10178590.44
      2789593.48     10178261.84
#Sta/Elev= 30
  4124.4 1299.41  4351.8 1290.52  4394.2 1287.82  4436.6 1286.93  4479.1 1285.38
  4582.2 1283.83  4712.4 1284.39  4889.8 1282.45  4902.7 1281.33  4939.8 1281.31
  4952.7 1279.10  4981.9 1277.71  4992.7 1276.37  4993.2 1275.87  5000.1 1276.37
  5011.0 1278.12  5017.3 1280.66  5039.9 1286.82  5046.4 1289.85  5061.0 1291.61
  5067.3 1291.47  5075.6 1293.75  5081.8 1294.10  5096.4 1298.43  5130.8 1300.73
  5144.6 1302.69  5175.6 1305.65  5275.5 1309.68  5286.9 1309.42  5291.7 1309.48
#Mann=8,-1,0
  4124.4    0.12       0  4436.6    0.05       0  4582.2    0.12       0
  4992.7    0.07       0  5000.1    0.12       0  5130.8    0.05       0
  5144.6    0.12       0  5286.9    0.05       0
Bank Sta=4992.7,5000.1
Exp/Cntr=0.3,0.1

Type RM Length L Ch R = 1,7988,269,269,269
BEGIN DESCRIPTION:
COTTONWOOD CREEK 02 17.0
END DESCRIPTION:
XS GIS Cut Line= 3
      2790355.68     10178903.10      2789971.05     10178541.46
      2789948.60     10178210.86
#Sta/Elev= 30
  4417.6 1291.58  4516.5 1288.10  4556.5 1287.42  4562.1 1287.28  4692.4 1283.79
  4721.6 1281.94  4728.9 1282.18  4771.4 1280.40  4785.6 1281.41  4822.6 1282.12
  4856.4 1282.64  4877.4 1282.08  4884.3 1281.33  4934.1 1281.57  4949.9 1280.54
  4963.9 1280.55  4974.0 1279.05  4984.0 1275.45  4990.3 1274.72  4990.8 1274.22
  4997.2 1274.22  4997.7 1274.72  5004.0 1276.03  5014.0 1276.47  5054.1 1284.40
  5090.4 1287.46  5144.3 1292.77  5194.5 1296.14  5204.5 1295.64  5276.9 1299.31
#Mann=8,-1,0
  4417.6    0.12       0  4556.5    0.05       0  4562.1    0.12       0
  4692.4    0.05       0  4822.6    0.12       0  4990.3    0.05       0
  4997.7    0.12       0  5090.4    0.12       0
Bank Sta=4990.3,4997.7
Exp/Cntr=0.3,0.1

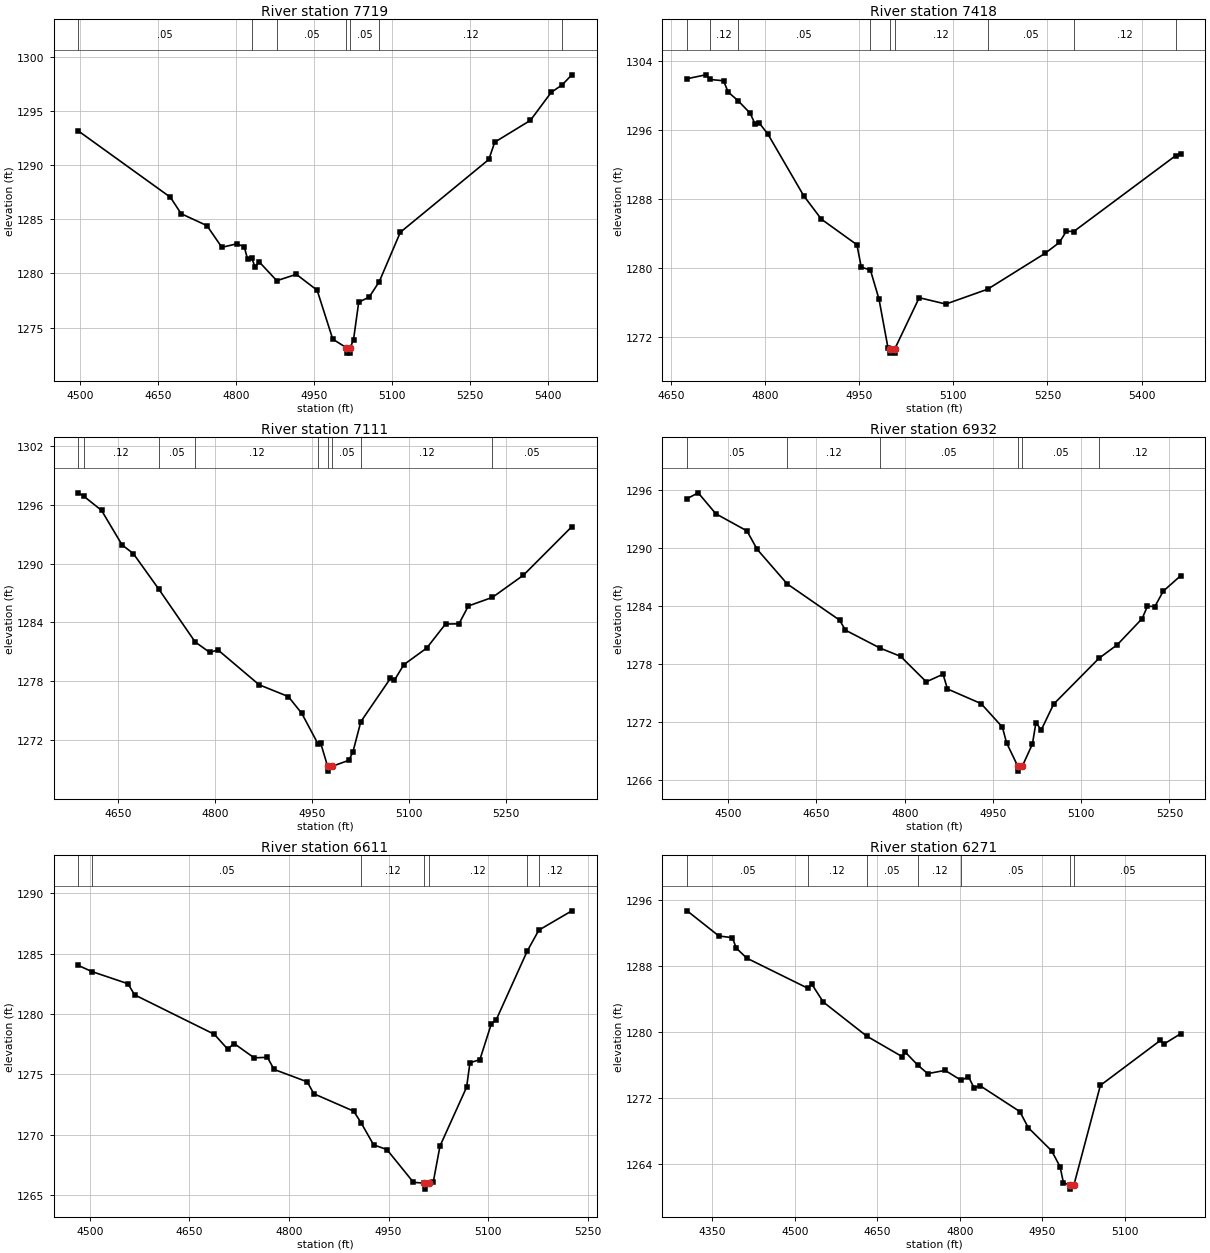
Type RM Length L Ch R = 1,7719,301,301,301
BEGIN DESCRIPTION:
COTTONWOOD CREEK 02 16.0
END DESCRIPTION:
XS GIS Cut Line= 3
      2790515.96     10178861.87      2790240.44     10178637.38
      2790213.91     10178043.46
#Sta/Elev= 30
  4496.3 1293.15  4673.6 1287.03  4694.4 1285.51  4744.0 1284.41  4772.7 1282.41
  4801.4 1282.73  4815.8 1282.46  4822.2 1281.32  4830.3 1281.40  4836.6 1280.60
  4844.5 1281.07  4878.4 1279.33  4916.0 1279.92  4956.1 1278.45  4986.1 1273.94
  5012.4 1273.15  5012.9 1272.65  5019.3 1272.65  5019.8 1273.15  5026.1 1273.90
  5036.1 1277.35  5056.2 1277.82  5075.5 1279.23  5116.2 1283.80  5286.4 1290.51
  5297.9 1292.11  5366.5 1294.12  5406.5 1296.70  5427.5 1297.39  5446.2 1298.32
#Mann=7,-1,0
  4496.3    0.05       0  4830.3    0.12       0  4878.4    0.05       0
  5012.4    0.05       0  5019.8    0.05       0  5075.5    0.12       0
  5427.5    0.05       0
Bank Sta=5012.4,5019.8
Exp/Cntr=0.3,0.1

Type RM Length L Ch R = 1,7418,307,307,307
BEGIN DESCRIPTION:
Mapping XS 41d7feb8
END DESCRIPTION:
XS GIS Cut Line= 3
      2790756.74     10178684.28      2790438.40     10178384.31
      2790291.51     10178068.07
#Sta/Elev= 30
  4676.1 1301.95  4705.8 1302.40  4712.4 1301.86  4734.1 1301.71  4741.4 1300.40
  4757.0 1299.41  4776.6 1297.93  4783.9 1296.74  4790.8 1296.82  4804.9 1295.49
  4861.6 1288.37  4889.9 1285.63  4946.5 1282.66  4953.4 1280.06  4968.0 1279.72
  4981.7 1276.33  4995.9 1270.71  4999.4 1270.57  4999.9 1270.07  5006.4 1270.07
  5006.9 1270.57  5045.7 1276.51  5088.1 1275.77  5154.5 1277.49  5246.1 1281.66
  5269.0 1282.93  5280.2 1284.25  5291.5 1284.18  5454.1 1293.01  5462.2 1293.26
#Mann=9,-1,0
  4676.1    0.05       0  4712.4    0.12       0  4757.0    0.05       0
  4968.0    0.12       0  4999.4    0.07       0  5006.9    0.12       0
  5154.5    0.05       0  5291.5    0.12       0  5454.1    0.05       0
Bank Sta=4999.4,5006.9
Exp/Cntr=0.3,0.1

Type RM Length L Ch R = 1,7111,179,179,179
BEGIN DESCRIPTION:
COTTONWOOD CREEK 02 15.0
END DESCRIPTION:
XS GIS Cut Line= 3
      2790799.63     10178527.15      2790697.65     10178238.83
      2790332.29     10177961.86
#Sta/Elev= 30
  4588.0 1297.21  4596.5 1296.87  4624.1 1295.42  4655.9 1291.90  4673.3 1291.02
  4712.5 1287.42  4769.1 1282.01  4791.6 1280.95  4804.4 1281.20  4868.1 1277.65
  4913.3 1276.45  4934.2 1274.73  4959.5 1271.60  4963.3 1271.74  4974.1 1269.35
  4974.6 1268.85  4981.6 1269.35  5006.9 1269.95  5013.2 1270.77  5025.6 1273.89
  5071.4 1278.30  5077.7 1278.13  5092.2 1279.70  5127.6 1281.39  5156.7 1283.84
  5177.5 1283.86  5192.1 1285.68  5229.4 1286.56  5277.4 1288.82  5352.3 1293.76
#Mann=9,-1,0
  4588.0    0.05       0  4596.5    0.12       0  4712.5    0.05       0
  4769.1    0.12       0  4959.5    0.05       0  4974.1    0.05       0
  4981.6    0.05       0  5025.6    0.12       0  5229.4    0.05       0
Bank Sta=4974.1,4981.6
Exp/Cntr=0.3,0.1

Type RM Length L Ch R = 1,6932,321,321,321
BEGIN DESCRIPTION:
Mapping XS 56c0f852
END DESCRIPTION:
XS GIS Cut Line= 3
      2790905.76     10178561.85      2790891.47     10178282.27
      2790582.30     10177816.48
#Sta/Elev= 30
  4430.2 1295.13  4449.0 1295.73  4479.0 1293.56  4531.9 1291.78  4549.1 1289.88
  4600.4 1286.28  4689.3 1282.53  4699.3 1281.49  4758.1 1279.63  4793.1 1278.77
  4836.7 1276.13  4865.2 1276.92  4872.7 1275.39  4929.9 1273.87  4966.0 1271.44
  4973.2 1269.80  4992.3 1267.37  4992.8 1266.87  4999.8 1267.37  5017.1 1269.68
  5023.1 1271.90  5032.1 1271.14  5053.2 1273.82  5130.2 1278.57  5161.4 1279.98
  5203.5 1282.68  5212.6 1283.97  5225.2 1283.94  5239.6 1285.54  5269.2 1287.14
#Mann=6,-1,0
  4430.2    0.05       0  4600.4    0.12       0  4758.1    0.05       0
  4992.3    0.05       0  4999.8    0.05       0  5130.2    0.12       0
Bank Sta=4992.3,4999.8
Exp/Cntr=0.3,0.1

Type RM Length L Ch R = 1,6611,340,340,340
BEGIN DESCRIPTION:
COTTONWOOD CREEK 02 14.0
END DESCRIPTION:
XS GIS Cut Line= 3
      2790977.19     10178368.01      2790991.48     10177743.48
      2790969.32     10177626.66
#Sta/Elev= 30
  4482.5 1284.03  4502.9 1283.52  4557.4 1282.51  4567.4 1281.59  4687.5 1278.32
  4707.5 1277.10  4717.5 1277.55  4747.5 1276.37  4767.5 1276.41  4777.5 1275.41
  4827.5 1274.38  4837.5 1273.39  4897.5 1271.95  4908.8 1270.97  4927.5 1269.16
  4947.5 1268.77  4987.5 1266.05  5003.8 1265.99  5004.3 1265.49  5011.3 1265.99
  5017.5 1266.12  5027.5 1269.06  5067.6 1273.94  5072.6 1275.96  5087.6 1276.22
  5104.9 1279.20  5112.1 1279.51  5158.8 1285.20  5176.4 1286.95  5226.1 1288.55
#Mann=7,-1,0
  4482.5    0.12       0  4502.9    0.05       0  4908.8    0.12       0
  5003.8    0.07       0  5011.3    0.12       0  5158.8    0.05       0
  5176.4    0.12       0
Bank Sta=5003.8,5011.3
Exp/Cntr=0.3,0.1

Type RM Length L Ch R = 1,6271,284,284,284
BEGIN DESCRIPTION:
COTTONWOOD CREEK 02 13.0
END DESCRIPTION:
XS GIS Cut Line= 3
      2791546.58     10178457.74      2791373.12     10177945.53
      2791185.34     10177641.42
#Sta/Elev= 30
  4304.0 1294.68  4361.7 1291.64  4386.4 1291.43  4393.4 1290.17  4412.5 1288.96
  4523.8 1285.31  4530.6 1285.84  4551.7 1283.65  4630.5 1279.54  4695.4 1277.04
  4700.7 1277.61  4723.8 1276.01  4741.8 1274.99  4773.4 1275.38  4803.1 1274.17
  4815.7 1274.64  4826.4 1273.24  4836.8 1273.54  4909.4 1270.40  4924.8 1268.45
  4967.3 1265.65  4982.7 1263.72  4988.7 1261.80  5000.2 1261.52  5000.7 1261.02
  5007.8 1261.52  5056.0 1273.57  5165.0 1279.00  5171.9 1278.58  5202.2 1279.82
#Mann=7,-1,0
  4304.0    0.05       0  4523.8    0.12       0  4630.5    0.05       0
  4723.8    0.12       0  4803.1    0.05       0  5000.2    0.05       0
  5007.8    0.05       0
Bank Sta=5000.2,5007.8
Exp/Cntr=0.3,0.1

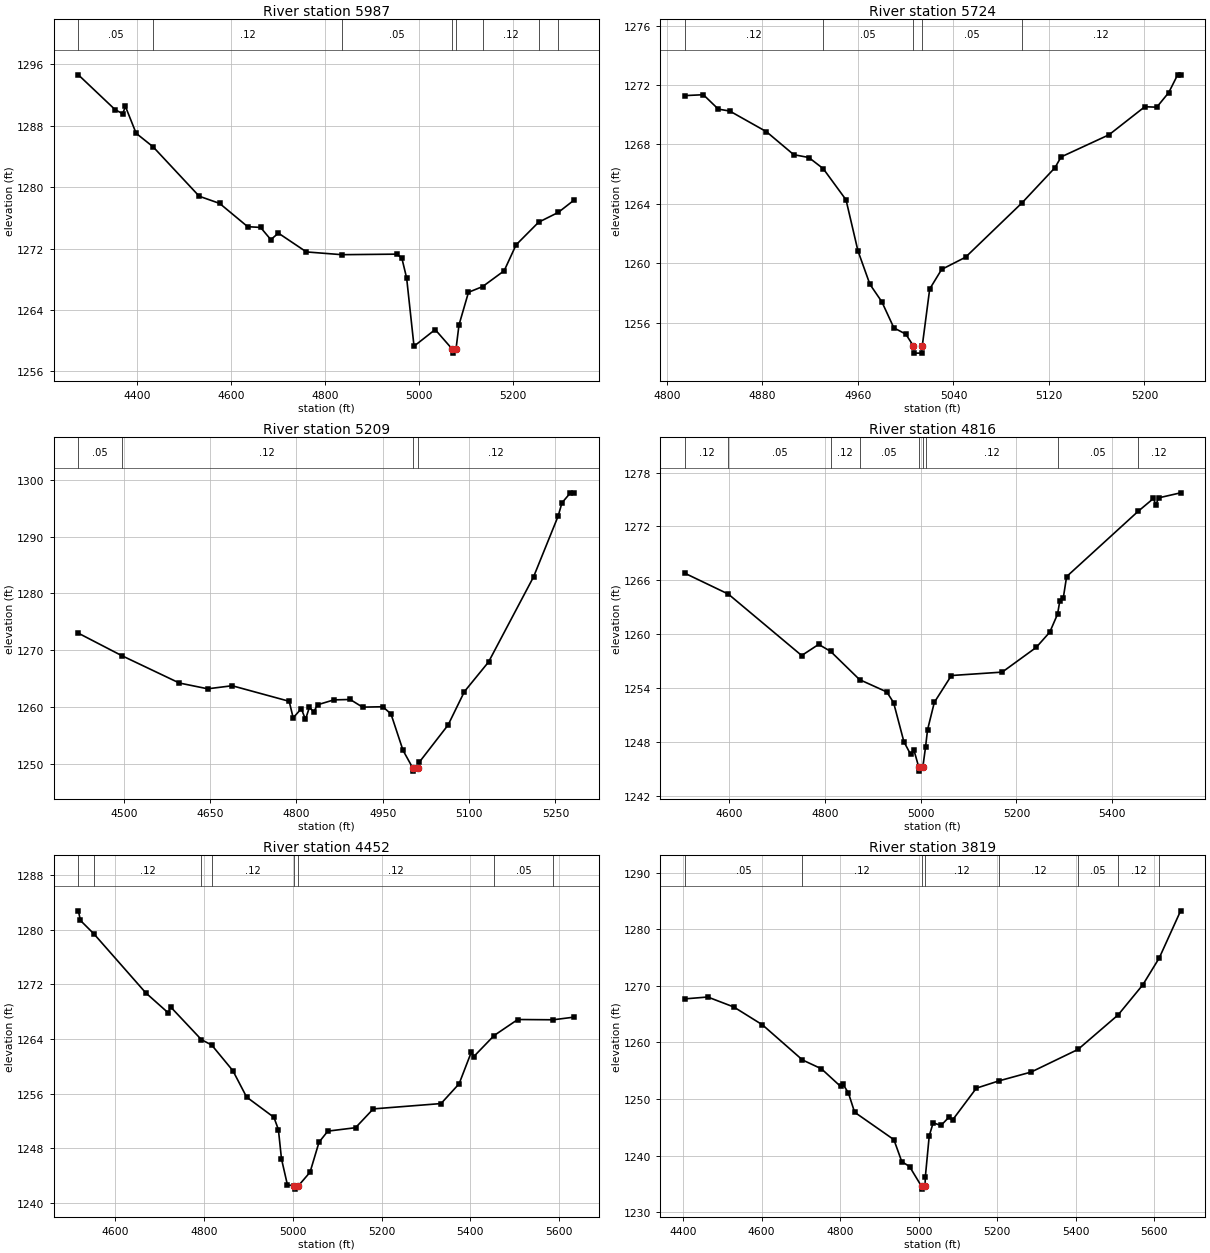
Type RM Length L Ch R = 1,5987,263,263,263
BEGIN DESCRIPTION:
Mapping XS b2965a5a
END DESCRIPTION:
XS GIS Cut Line= 3
      2791926.20     10178210.87      2791630.26     10177674.09
      2791193.49     10177604.70
#Sta/Elev= 30
  4275.2 1294.65  4353.5 1290.11  4369.6 1289.58  4375.4 1290.53  4398.2 1287.03
  4434.4 1285.26  4532.4 1278.83  4575.9 1277.89  4635.5 1274.86  4663.0 1274.76
  4684.8 1273.17  4700.9 1274.02  4760.5 1271.57  4835.8 1271.21  4953.5 1271.28
  4963.7 1270.74  4973.8 1268.17  4989.5 1259.28  5034.5 1261.45  5071.2 1258.88
  5071.7 1258.38  5078.8 1258.88  5085.2 1262.05  5105.4 1266.31  5135.4 1267.05
  5181.3 1269.11  5206.7 1272.49  5254.6 1275.44  5296.5 1276.72  5330.4 1278.34
#Mann=8,-1,0
  4275.2    0.05       0  4434.4    0.12       0  4835.8    0.05       0
  5071.2    0.05       0  5078.8    0.05       0  5135.4    0.12       0
  5254.6    0.05       0  5296.5    0.12       0
Bank Sta=5071.2,5078.8
Exp/Cntr=0.3,0.1

Type RM Length L Ch R = 1,5724,515,515,515
BEGIN DESCRIPTION:
COTTONWOOD CREEK 02 12.0
END DESCRIPTION:
XS GIS Cut Line= 3
      2791609.87     10177367.96      2791503.87     10177417.25
      2791205.71     10177403.11
#Sta/Elev= 30
  4814.9 1271.29  4830.5 1271.35  4843.0 1270.38  4852.6 1270.25  4883.3 1268.86
  4906.2 1267.31  4918.8 1267.12  4930.9 1266.37  4950.0 1264.27  4960.0 1260.83
  4970.0 1258.58  4980.0 1257.40  4990.1 1255.64  5000.1 1255.22  5006.3 1254.44
  5006.8 1253.94  5013.4 1253.94  5013.9 1254.44  5020.1 1258.26  5030.1 1259.58
  5050.1 1260.40  5097.5 1264.07  5125.0 1266.43  5130.2 1267.16  5170.3 1268.65
  5200.3 1270.54  5210.3 1270.51  5220.3 1271.49  5227.8 1272.69  5230.3 1272.69
#Mann=5,-1,0
  4814.9    0.12       0  4930.9    0.05       0  5006.3    0.05       0
  5013.9    0.05       0  5097.5    0.12       0
Bank Sta=5006.3,5013.9
Exp/Cntr=0.3,0.1

Type RM Length L Ch R = 1,5209,393,393,393
BEGIN DESCRIPTION:
COTTONWOOD CREEK 02 11.0
END DESCRIPTION:
XS GIS Cut Line= 3
      2792044.52     10177382.21      2791717.16     10177037.96
      2791455.70     10176753.13
#Sta/Elev= 30
  4421.0 1273.01  4496.1 1269.07  4596.5 1264.23  4645.8 1263.21  4688.3 1263.75
  4787.4 1261.01  4794.3 1258.10  4808.5 1259.71  4815.7 1257.81  4822.6 1259.97
  4829.9 1259.12  4836.8 1260.40  4865.1 1261.26  4893.4 1261.33  4914.9 1259.98
  4950.1 1260.05  4964.3 1258.78  4985.2 1252.37  5002.4 1249.21  5002.9 1248.71
  5011.2 1249.21  5013.6 1250.30  5063.5 1256.83  5091.9 1262.72  5133.8 1267.93
  5212.1 1282.94  5254.7 1293.61  5261.4 1295.97  5275.6 1297.67  5282.7 1297.73
#Mann=4,-1,0
  4421.0    0.05       0  4496.1    0.12       0  5002.4    0.07       0
  5011.2    0.12       0
Bank Sta=5002.4,5011.2
Exp/Cntr=0.3,0.1

Type RM Length L Ch R = 1,4816,364,364,364
BEGIN DESCRIPTION:
COTTONWOOD CREEK 02 10.0
END DESCRIPTION:
XS GIS Cut Line= 4
      2792238.41     10177072.00      2792031.23     10176798.57
      2791705.68     10176453.11      2791490.03     10176433.31
#Sta/Elev= 30
  4508.1 1266.79  4599.0 1264.46  4752.0 1257.61  4787.4 1258.85  4812.2 1258.08
  4872.8 1254.92  4929.5 1253.55  4943.7 1252.36  4965.2 1248.00  4979.3 1246.58
  4986.2 1247.06  4995.9 1245.22  4996.4 1244.72  5004.8 1245.22  5010.4 1247.41
  5014.5 1249.32  5028.7 1252.39  5064.3 1255.38  5170.3 1255.76  5241.1 1258.51
  5269.4 1260.21  5285.7 1262.22  5290.4 1263.69  5297.7 1264.04  5304.6 1266.41
  5453.6 1273.68  5485.7 1275.12  5490.7 1274.41  5496.6 1275.19  5542.4 1275.75
#Mann=9,-1,0
  4508.1    0.12       0  4599.0    0.05       0  4812.2    0.12       0
  4872.8    0.05       0  4995.9    0.05       0  5004.8    0.05       0
  5010.4    0.12       0  5285.7    0.05       0  5453.6    0.12       0
Bank Sta=4995.9,5004.8
Exp/Cntr=0.3,0.1

Type RM Length L Ch R = 1,4452,633,633,633
BEGIN DESCRIPTION:
COTTONWOOD CREEK 02 9.0
END DESCRIPTION:
XS GIS Cut Line= 3
      2792652.74     10176569.99      2792258.85     10176467.95
      2791560.84     10176335.29
#Sta/Elev= 30
  4516.6 1282.74  4521.4 1281.33  4552.1 1279.34  4668.5 1270.75  4719.2 1267.82
  4724.4 1268.70  4794.0 1263.90  4817.1 1263.12  4864.8 1259.37  4895.8 1255.51
  4957.3 1252.55  4967.4 1250.76  4974.4 1246.46  4987.8 1242.66  5003.6 1242.55
  5004.1 1242.05  5012.6 1242.55  5038.7 1244.52  5059.0 1248.92  5078.8 1250.53
  5141.2 1251.03  5181.2 1253.78  5333.9 1254.56  5374.6 1257.45  5402.3 1262.11
  5407.4 1261.41  5453.5 1264.51  5506.8 1266.85  5586.6 1266.81  5634.0 1267.20
#Mann=8,-1,0
  4516.6    0.05       0  4552.1    0.12       0  4794.0    0.05       0
  4817.1    0.12       0  5003.6    0.07       0  5012.6    0.12       0
  5453.5    0.05       0  5586.6    0.12       0
Bank Sta=5003.6,5012.6
Exp/Cntr=0.3,0.1

Type RM Length L Ch R = 1,3819,531,531,531
BEGIN DESCRIPTION:
COTTONWOOD CREEK 02 8.0
END DESCRIPTION:
XS GIS Cut Line= 3
      2792430.31     10176072.04      2792041.37     10175921.28
      2791195.55     10175951.61
#Sta/Elev= 30
  4404.0 1267.70  4462.6 1268.03  4528.9 1266.27  4602.0 1263.11  4704.0 1256.90
  4752.2 1255.34  4801.3 1252.21  4806.7 1252.68  4821.1 1251.05  4836.8 1247.66
  4936.9 1242.81  4956.9 1238.94  4976.9 1238.04  5007.3 1234.56  5007.8 1234.06
  5016.4 1234.56  5016.9 1236.12  5027.0 1243.50  5037.0 1245.78  5057.0 1245.32
  5077.0 1246.77  5087.0 1246.34  5147.0 1251.91  5204.5 1253.20  5286.5 1254.76
  5406.0 1258.76  5508.3 1264.87  5571.1 1270.18  5613.0 1274.93  5667.5 1283.27
#Mann=8,-1,0
  4404.0    0.05       0  4704.0    0.12       0  5007.3    0.07       0
  5016.4    0.12       0  5204.5    0.12       0  5406.0    0.05       0
  5508.3    0.12       0  5613.0    0.05       0
Bank Sta=5007.3,5016.4
Exp/Cntr=0.3,0.1

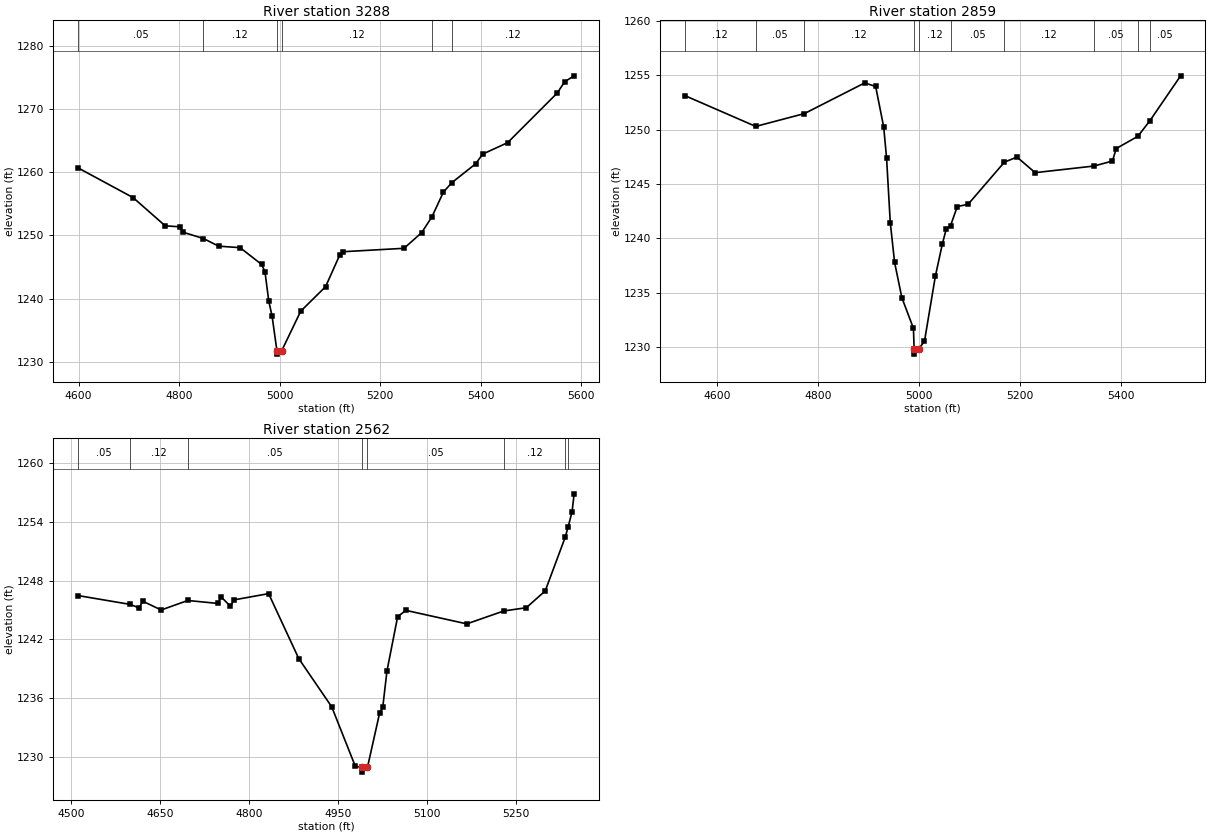
Type RM Length L Ch R = 1,3288,429,429,429
BEGIN DESCRIPTION:
COTTONWOOD CREEK 02 7.0
END DESCRIPTION:
XS GIS Cut Line= 3
      2792401.74     10175731.23      2791985.37     10175367.93
      2791649.62     10175093.22
#Sta/Elev= 30
  4599.2 1260.70  4708.6 1255.99  4772.2 1251.53  4800.7 1251.38  4807.3 1250.53
  4848.2 1249.52  4878.5 1248.31  4921.2 1248.07  4964.0 1245.41  4970.6 1244.28
  4978.2 1239.61  4984.8 1237.23  4994.5 1231.70  4995.0 1231.20  5003.7 1231.70
  5041.8 1238.01  5091.2 1241.89  5119.6 1246.95  5126.3 1247.43  5247.3 1247.97
  5282.4 1250.46  5302.9 1252.98  5325.5 1256.87  5342.5 1258.38  5389.4 1261.34
  5403.8 1262.90  5453.3 1264.71  5552.3 1272.60  5566.7 1274.37  5585.6 1275.30
#Mann=6,-1,0
  4599.2    0.05       0  4848.2    0.12       0  4994.5    0.07       0
  5003.7    0.12       0  5302.9    0.05       0  5342.5    0.12       0
Bank Sta=4994.5,5003.7
Exp/Cntr=0.3,0.1

Type RM Length L Ch R = 1,2859,297,297,297
BEGIN DESCRIPTION:
COTTONWOOD CREEK 02 6.0
END DESCRIPTION:
XS GIS Cut Line= 3
      2792738.41     10175474.02      2792497.63     10175223.03
      2791944.59     10174910.80
#Sta/Elev= 30
  4535.5 1253.13  4676.3 1250.29  4772.8 1251.47  4892.3 1254.29  4914.0 1253.96
  4929.9 1250.25  4935.6 1247.40  4943.0 1241.44  4951.5 1237.80  4965.9 1234.55
  4988.9 1231.73  4990.2 1229.86  4990.7 1229.36  4999.4 1229.86  5010.7 1230.53
  5032.4 1236.54  5046.3 1239.51  5054.0 1240.88  5062.4 1241.16  5075.7 1242.92
  5097.4 1243.14  5169.2 1247.01  5194.1 1247.47  5230.1 1246.04  5347.0 1246.65
  5383.3 1247.11  5390.8 1248.26  5433.7 1249.38  5457.6 1250.82  5518.4 1254.94
#Mann=10,-1,0
  4535.5    0.12       0  4676.3    0.05       0  4772.8    0.12       0
  4990.2    0.07       0  4999.4    0.12       0  5062.4    0.05       0
  5169.2    0.12       0  5347.0    0.05       0  5433.7    0.12       0
  5457.6    0.05       0
Bank Sta=4990.2,4999.4
Exp/Cntr=0.3,0.1

Type RM Length L Ch R = 1,2562,462,462,462
BEGIN DESCRIPTION:
COTTONWOOD CREEK 02 5.0
END DESCRIPTION:
XS GIS Cut Line= 3
      2792724.14     10175225.04      2792543.70     10174923.38
      2792090.04     10174755.89
#Sta/Elev= 30
  4512.5 1246.47  4600.0 1245.57  4615.2 1245.21  4621.0 1245.90  4652.2 1245.00
  4697.0 1245.97  4747.5 1245.67  4753.3 1246.33  4768.9 1245.37  4774.7 1246.03
  4833.1 1246.67  4883.9 1240.03  4939.4 1235.10  4979.2 1229.01  4990.3 1228.93
  4990.8 1228.43  4999.6 1228.93  5020.0 1234.46  5025.3 1235.06  5032.4 1238.77
  5050.4 1244.32  5064.4 1244.96  5166.8 1243.58  5229.1 1244.90  5267.0 1245.23
  5298.9 1246.95  5332.7 1252.46  5337.6 1253.53  5344.0 1255.01  5347.6 1256.87
#Mann=8,-1,0
  4512.5    0.05       0  4600.0    0.12       0  4697.0    0.05       0
  4990.3    0.05       0  4999.6    0.05       0  5229.1    0.12       0
  5332.7    0.05       0  5337.6    0.12       0
Bank Sta=4990.3,4999.6
Exp/Cntr=0.3,0.1