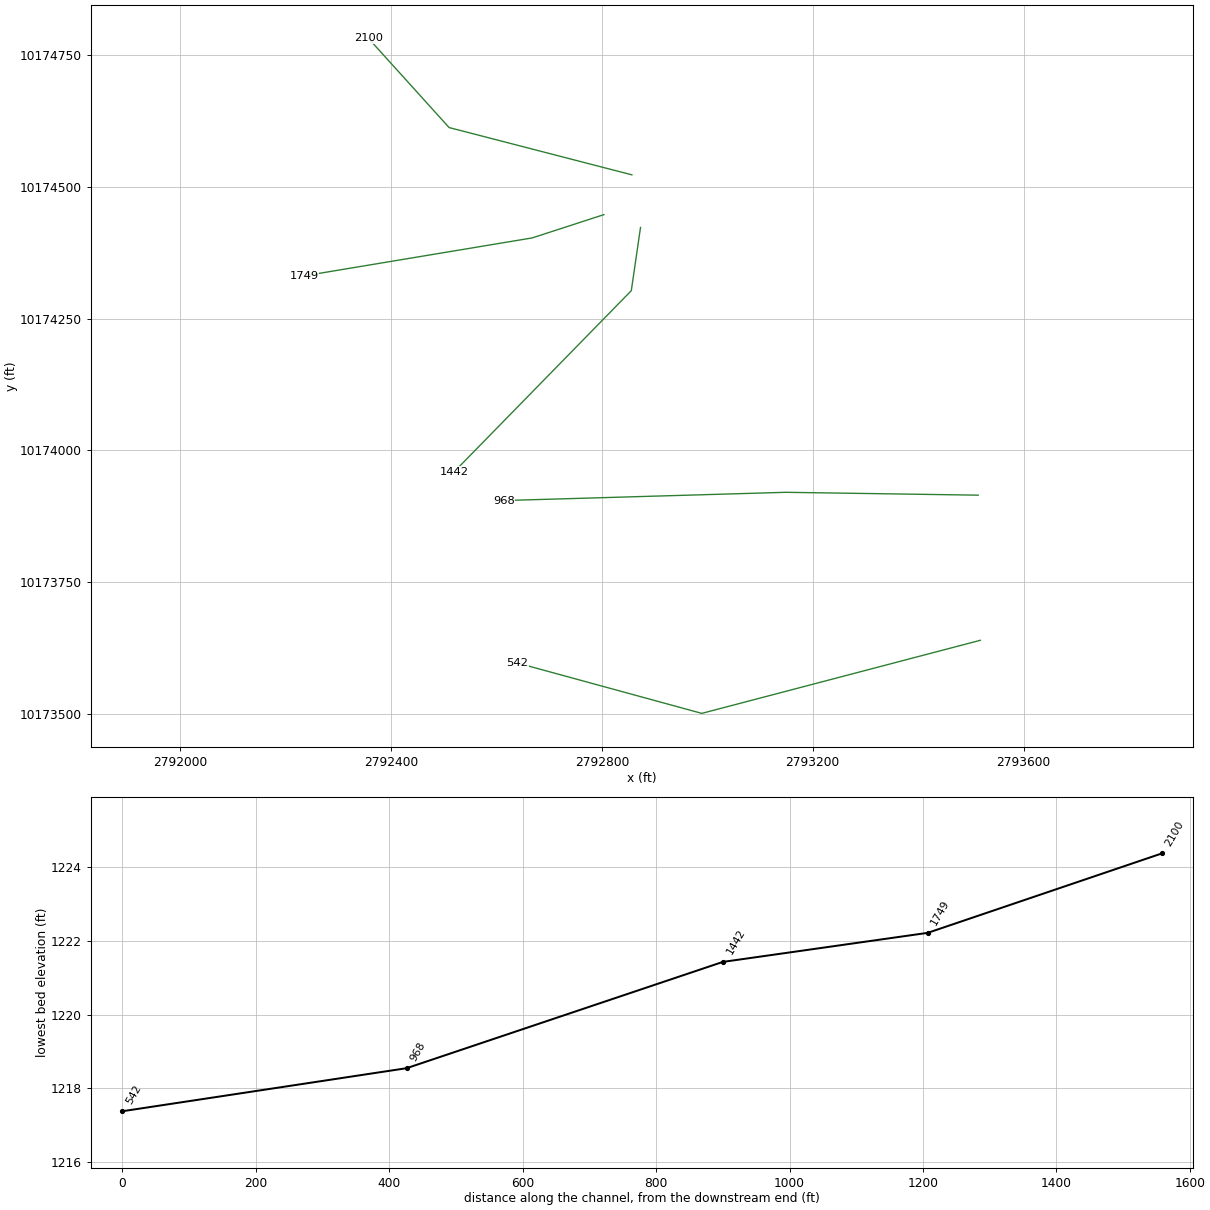
HEC-RAS study COTTONWOOD CREEK 02.prj: COTTONWOOD CREEK 02 Base Level Engineering

--- COTTONWOOD CREEK 02.g01 (geometry) --- (continued)

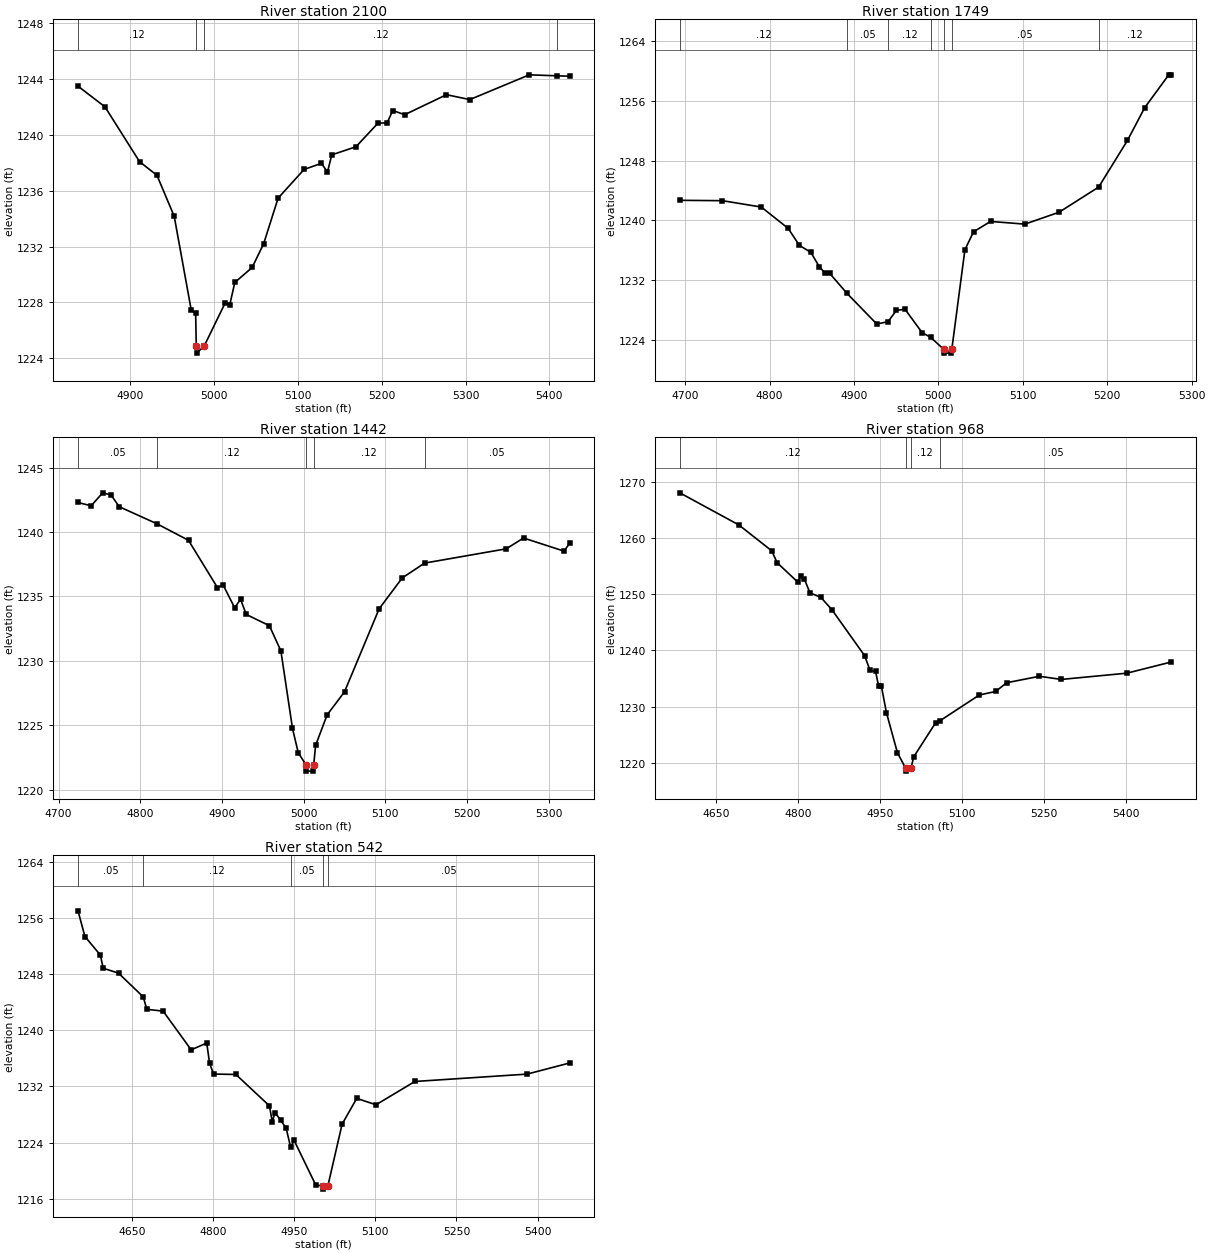
Type RM Length L Ch R = 1,2100,351,351,351
BEGIN DESCRIPTION:
Mapping XS 2eecbf94
END DESCRIPTION:
XS GIS Cut Line= 3
      2792856.84     10174523.01      2792509.87     10174612.81
      2792356.81     10174782.20
#Sta/Elev= 30
  4837.5 1243.46  4869.7 1241.98  4911.0 1238.06  4931.7 1237.09  4952.3 1234.16
  4972.7 1227.43  4977.9 1227.22  4978.6 1224.88  4979.1 1224.38  4988.0 1224.88
  5013.3 1227.99  5018.5 1227.81  5024.6 1229.43  5045.3 1230.50  5059.1 1232.21
  5076.3 1235.46  5107.3 1237.51  5127.9 1237.94  5135.2 1237.33  5140.3 1238.55
  5169.2 1239.13  5195.5 1240.82  5206.3 1240.83  5213.1 1241.72  5227.3 1241.42
  5277.2 1242.85  5305.0 1242.50  5376.0 1244.27  5408.9 1244.20  5424.2 1244.17
#Mann=4,-1,0
  4837.5    0.12       0  4978.6    0.07       0  4988.0    0.12       0
  5408.9    0.05       0
Bank Sta=4978.6,4988
Exp/Cntr=0.3,0.1

Type RM Length L Ch R = 1,1749,307,307,307
BEGIN DESCRIPTION:
COTTONWOOD CREEK 02 4.0
END DESCRIPTION:
XS GIS Cut Line= 3
      2792803.75     10174447.50      2792667.57     10174403.26
      2792234.32     10174331.17
#Sta/Elev= 30
  4693.7 1242.69  4744.2 1242.64  4790.2 1241.79  4822.1 1238.93  4835.3 1236.66
  4848.9 1235.72  4859.1 1233.77  4866.2 1232.89  4871.3 1232.90  4891.7 1230.23
  4927.1 1226.11  4940.4 1226.44  4950.3 1227.96  4960.5 1228.09  4980.7 1224.97
  4991.0 1224.32  5006.4 1222.72  5006.9 1222.22  5015.4 1222.22  5015.9 1222.72
  5031.4 1236.06  5041.6 1238.47  5061.8 1239.86  5102.4 1239.50  5142.9 1241.09
  5189.8 1244.46  5224.0 1250.72  5244.3 1255.09  5272.9 1259.50  5276.1 1259.50
#Mann=7,-1,0
  4693.7    0.12       0  4891.7    0.05       0  4940.4    0.12       0
  4991.0    0.05       0  5006.4    0.05       0  5015.9    0.05       0
  5189.8    0.12       0
Bank Sta=5006.4,5015.9
Exp/Cntr=0.3,0.1

Type RM Length L Ch R = 1,1442,474,474,474
BEGIN DESCRIPTION:
COTTONWOOD CREEK 02 3.0
END DESCRIPTION:
XS GIS Cut Line= 3
      2792873.15     10174423.05      2792855.68     10174303.11
      2792519.59     10173959.29
#Sta/Elev= 30
  4723.8 1242.30  4739.9 1242.04  4754.0 1243.05  4764.2 1242.89  4774.3 1241.97
  4820.3 1240.65  4859.1 1239.36  4894.5 1235.69  4901.5 1235.89  4915.6 1234.12
  4922.8 1234.78  4929.8 1233.60  4958.1 1232.73  4972.2 1230.77  4986.4 1224.75
  4993.5 1222.85  5002.9 1221.93  5003.4 1221.43  5011.9 1221.43  5012.4 1221.93
  5014.7 1223.43  5028.8 1225.80  5050.1 1227.59  5092.5 1234.04  5120.8 1236.44
  5148.1 1237.59  5248.1 1238.70  5269.3 1239.54  5318.9 1238.52  5325.8 1239.14
#Mann=5,-1,0
  4723.8    0.05       0  4820.3    0.12       0  5002.9    0.07       0
  5012.4    0.12       0  5148.1    0.05       0
Bank Sta=5002.9,5012.4
Exp/Cntr=0.3,0.1

Type RM Length L Ch R = 1,968,426,426,426
BEGIN DESCRIPTION:
COTTONWOOD CREEK 02 2.0
END DESCRIPTION:
XS GIS Cut Line= 3
      2793514.00     10173914.84      2793149.12     10173920.28
      2792613.97     10173904.64
#Sta/Elev= 30
  4583.7 1268.04  4692.0 1262.32  4752.0 1257.73  4762.0 1255.60  4800.1 1252.13
  4805.1 1253.25  4812.0 1252.65  4822.0 1250.25  4842.0 1249.44  4862.0 1247.28
  4922.1 1239.08  4932.1 1236.46  4942.1 1236.29  4947.8 1233.65  4952.8 1233.65
  4962.1 1228.93  4982.1 1221.84  4997.3 1219.04  4997.8 1218.54  5006.9 1219.04
  5012.1 1221.09  5052.1 1227.14  5059.8 1227.48  5132.1 1232.08  5162.1 1232.71
  5182.2 1234.26  5242.2 1235.41  5282.2 1234.85  5402.2 1235.96  5484.0 1237.96
#Mann=4,-1,0
  4583.7    0.12       0  4997.3    0.07       0  5006.9    0.12       0
  5059.8    0.05       0
Bank Sta=4997.3,5006.9
Exp/Cntr=0.3,0.1

Type RM Length L Ch R = 1,542,0,0,0
BEGIN DESCRIPTION:
COTTONWOOD CREEK 02 1.0
END DESCRIPTION:
XS GIS Cut Line= 3
      2793518.09     10173639.33      2792989.47     10173500.55
      2792639.54     10173596.17
#Sta/Elev= 30
  4550.1 1257.03  4562.9 1253.37  4591.5 1250.72  4596.7 1248.85  4625.0 1248.15
  4670.7 1244.77  4677.4 1242.99  4707.5 1242.74  4759.4 1237.22  4788.2 1238.19
  4793.4 1235.32  4800.7 1233.77  4842.1 1233.71  4904.1 1229.24  4909.3 1227.00
  4914.5 1228.27  4924.8 1227.22  4935.1 1226.02  4943.4 1223.33  4949.7 1224.32
  4990.0 1217.92  5002.7 1217.87  5003.2 1217.37  5012.3 1217.87  5038.5 1226.63
  5065.6 1230.30  5101.2 1229.39  5173.1 1232.71  5380.5 1233.76  5459.4 1235.35
#Mann=5,-1,0
  4550.1    0.05       0  4670.7    0.12       0  4943.4    0.05       0
  5002.7    0.03       0  5012.3    0.05       0
Bank Sta=5002.7,5012.3
Exp/Cntr=0.3,0.1

Chan Stop Cuts=-1