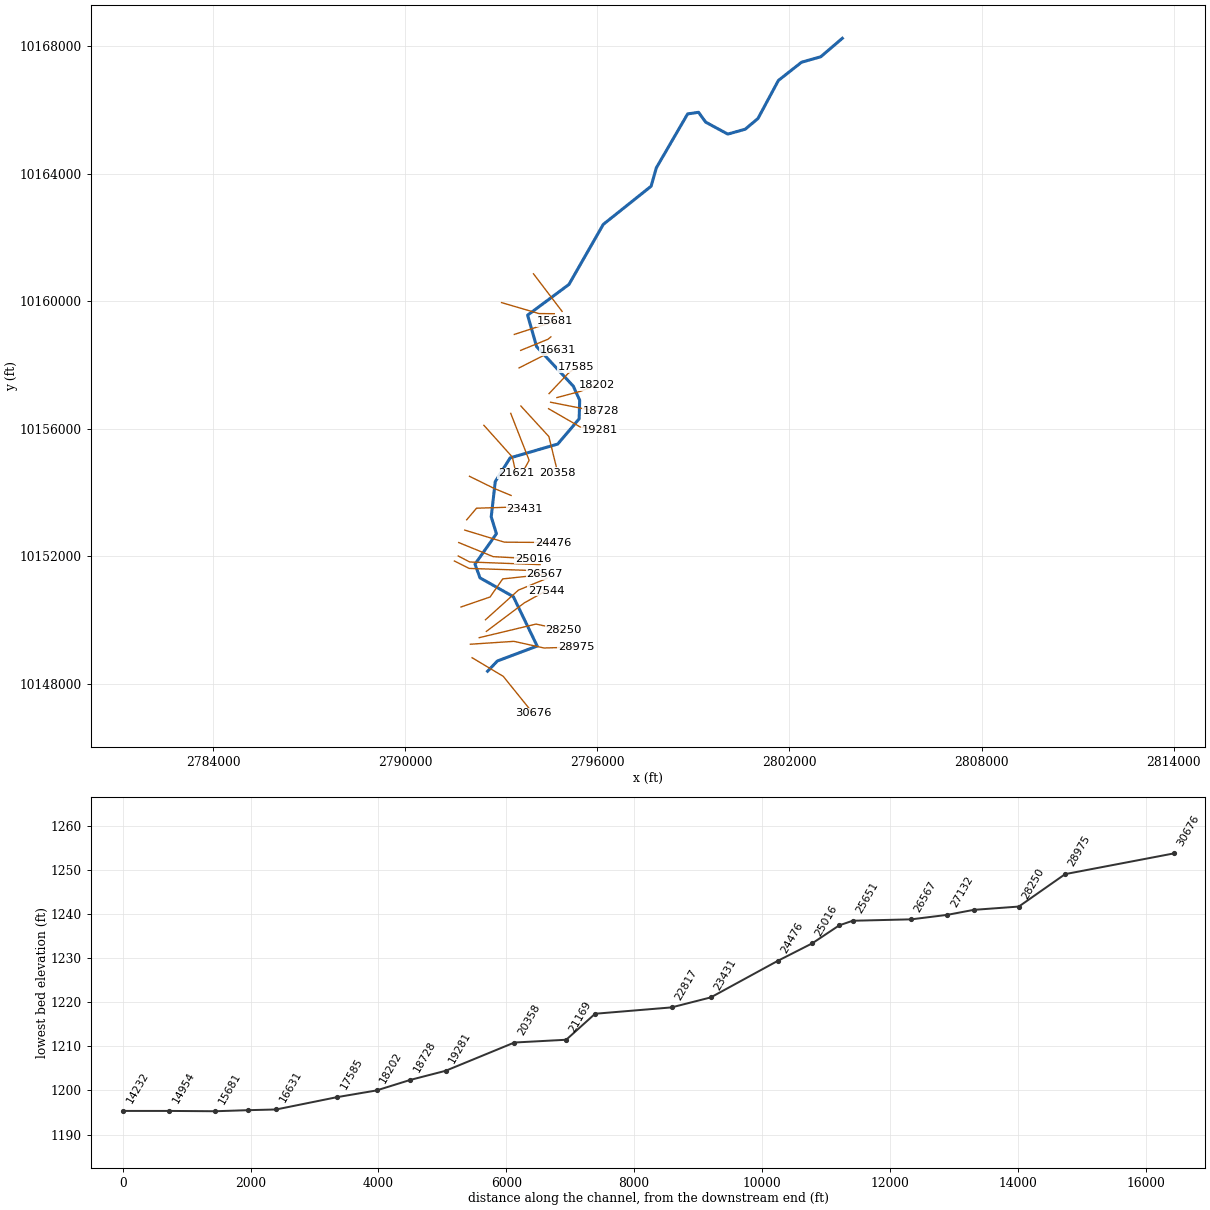
--- CRABAPPLE CREEK.prj (project) ---

Proj Title=CRABAPPLE CREEK Base Level Engineering
Current Plan=p01
Default Exp/Contr=0.3,0.1
English Units
Geom File=g01
Flow File=f01
Plan File=p01
Y Axis Title=Elevation
X Axis Title(PF)=Main Channel Distance
X Axis Title(XS)=Station
BEGIN DESCRIPTION:
CRABAPPLE CREEK
END DESCRIPTION:
DSS Export Rating Curves= 0
DSS Export Rating Curve Sorted= 0
DSS Export Volume Flow Curves= 0
DXF OffsetX= 0
DXF OffsetY= 0
DXF ScaleX= 1
DXF ScaleY= 10

--- CRABAPPLE CREEK.p01 (plan) ---

Plan Title=Multiple Run
Short Identifier=Multiple
Geom File=g01
Flow File=f01
Subcritical Flow
K Sum by GR= 0
Std Step Tol= 0.01
Critical Tol= 0.01
Num of Std Step Trials= 20
Max Error Tol= 0.3
Flow Tol Ratio= 0.001
Split Flow NTrial= 30
Split Flow Tol= 0.02
Split Flow Ratio= 0.02
Log Output Level= 0
Friction Slope Method= 1
Unsteady Friction Slope Method= 2
Unsteady Bridges Friction Slope Method= 1
Parabolic Critical Depth
Global Vel Dist=  1 , 1 , 1
Global Log Level= 0
CheckData=True
Encroach Param= -1, 0, 0, 0
BEGIN DESCRIPTION:
Multiple Run
END DESCRIPTION:

--- CRABAPPLE CREEK.f01 (steady flow) ---

Flow Title=Multiple
Program Version=4.10
Number of Profiles= 7
Profile Names=10-year,25-year,50-year,1pct_min,100-year,1pct_plu,500-year
River Rch & RM=CRABAPPLE CREEK,Reach-1         ,30676
   18022   33385   50952   37761   71802  136530   92547
River Rch & RM=CRABAPPLE CREEK,Reach-1         ,28975
   18247   33779   51481   38116   72505  137917   93394
River Rch & RM=CRABAPPLE CREEK,Reach-1         ,27544
   18011   33340   50787   37642   71524  135902   92123
River Rch & RM=CRABAPPLE CREEK,Reach-1         ,25651
   18342   33919   51569   38171   72564  137947   93384
River Rch & RM=CRABAPPLE CREEK,Reach-1         ,22817
   20567   37738   56494   41390   78939  150552  100879
River Rch & RM=CRABAPPLE CREEK,Reach-1         ,21621
   20567   37738   56494   41390   78939  150552  100879
River Rch & RM=CRABAPPLE CREEK,Reach-1         ,14954
   20410   37446   56034   41074   78287  149214  100034
River Rch & RM=CRABAPPLE CREEK,Reach-1         ,12856
   21624   39520   58691   42794   81710  156015  104049
River Rch & RM=CRABAPPLE CREEK,Reach-1         ,10740
   21026   38414   56995   41632   79326  151150  100984
River Rch & RM=CRABAPPLE CREEK,Reach-1         ,4711
   20700   37802   56027   40960   77946  148330   99189
Boundary for River Rch & Prof#=CRABAPPLE CREEK,Reach-1         , 1
Up Type= 0
Dn Type= 3
Dn Slope=0.005
Boundary for River Rch & Prof#=CRABAPPLE CREEK,Reach-1         , 2
Up Type= 0
Dn Type= 3
Dn Slope=0.005
Boundary for River Rch & Prof#=CRABAPPLE CREEK,Reach-1         , 3
Up Type= 0
Dn Type= 3
Dn Slope=0.005
Boundary for River Rch & Prof#=CRABAPPLE CREEK,Reach-1         , 4
Up Type= 0
Dn Type= 3
Dn Slope=0.005
Boundary for River Rch & Prof#=CRABAPPLE CREEK,Reach-1         , 5
Up Type= 0
Dn Type= 3
Dn Slope=0.005
Boundary for River Rch & Prof#=CRABAPPLE CREEK,Reach-1         , 6
Up Type= 0
Dn Type= 3
Dn Slope=0.005
Boundary for River Rch & Prof#=CRABAPPLE CREEK,Reach-1         , 7
Up Type= 0
Dn Type= 3
Dn Slope=0.005
DSS Import GetInterval= 0
DSS Import GetPeak= 0
DSS Import FillOption= 0

--- CRABAPPLE CREEK.g01 (geometry) ---

Geom Title=Existing Conditions
Program Version=4.10

River Reach=CRABAPPLE CREEK ,Reach-1
Reach XY= 30
      2792572.41     10148389.07      2792877.86     10148710.18
        2794120.       10149179.      2793376.25       10150728.
      2792333.75       10151318.       2792179.5       10151747.
       2792847.5       10152702.      2792685.25       10153231.
        2792811.       10154337.      2793275.75       10155080.
      2794763.25       10155515.       2795431.5       10156305.
      2795448.25       10156888.      2795250.25       10157328.
        2794103.       10158570.      2793821.75       10159557.
       2795112.5       10160520.      2796184.75       10162404.
      2797679.75       10163602.      2797841.25       10164176.
      2798819.75       10165870.        2799160.       10165920.
        2799384.       10165611.       2800074.5       10165236.
       2800620.5       10165391.      2801017.25       10165727.
       2801654.5       10166919.      2802378.25       10167491.
        2802976.       10167662.      2803651.75       10168240.

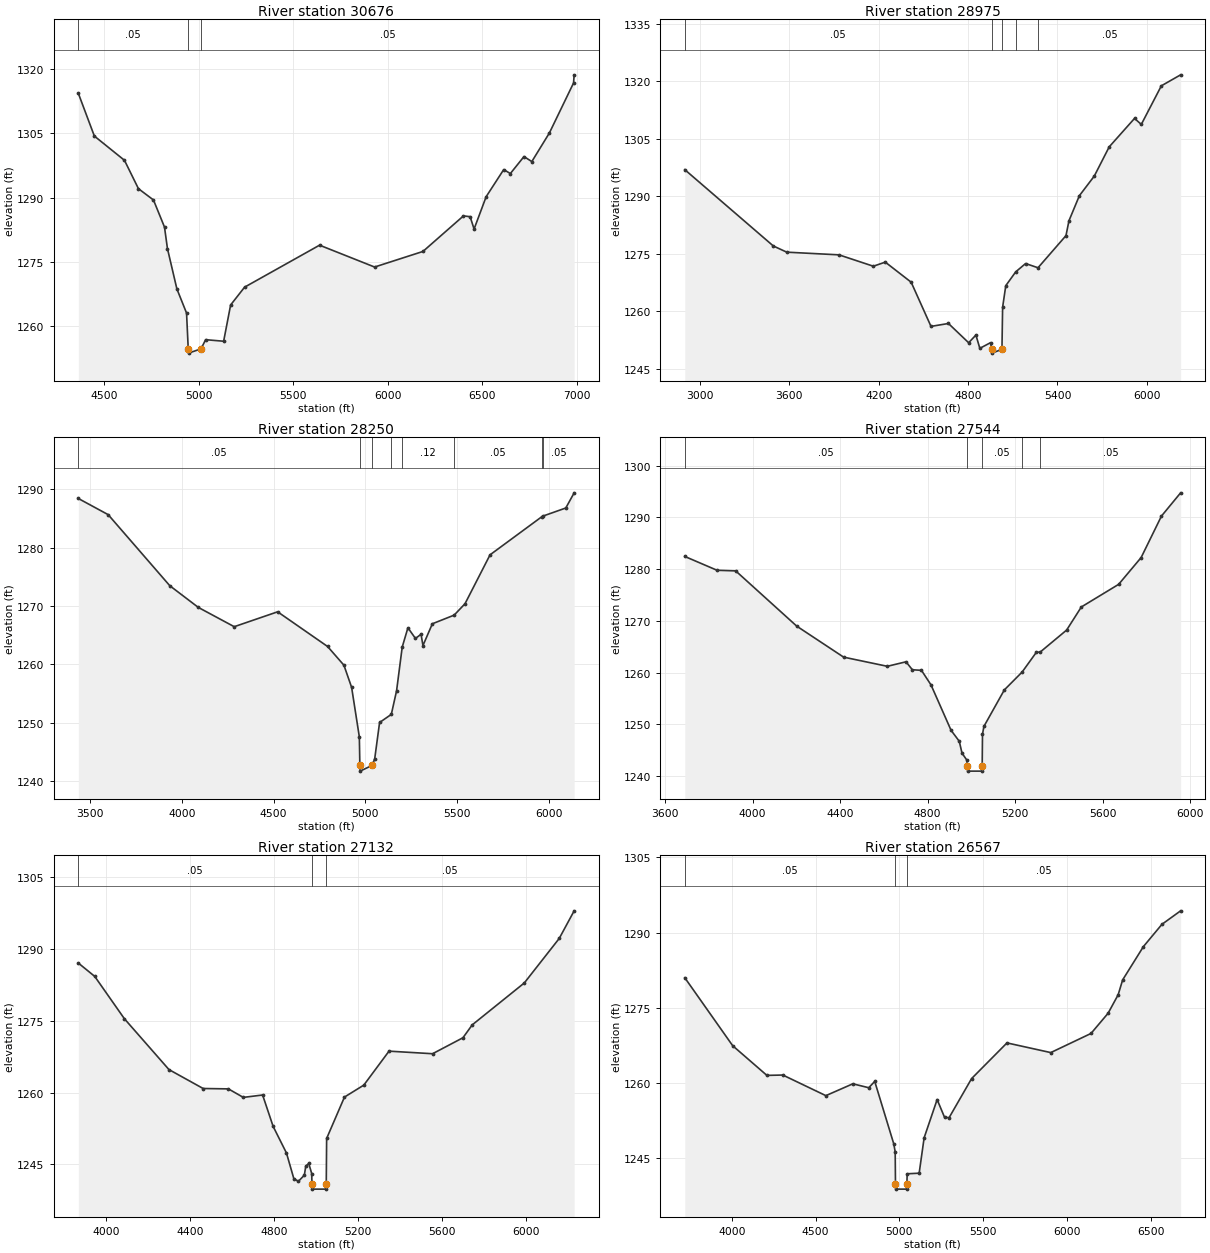
Type RM Length L Ch R = 1 ,30676   ,1701,1701,1701
BEGIN DESCRIPTION:
CRABAPPLE CREEK 42.0
END DESCRIPTION:
XS GIS Cut Line= 3
      2792088.47     10148812.05      2793060.65     10148228.74
      2793993.66     10147066.82
#Sta/Elev= 30
  4363.3 1314.28  4448.1 1304.33  4607.5 1298.68  4681.3 1292.08    4761 1289.44
  4819.3 1283.13  4834.9 1278.12  4884.8 1268.74    4936 1263.11  4944.9 1254.78
  4946.4 1253.78  5012.6 1254.78    5037 1256.91  5132.3 1256.55  5169.2 1264.99
  5243.1 1269.14  5639.9 1278.92  5931.1 1273.83  6187.1 1277.46  6401.5 1285.74
  6436.7 1285.55  6457.6 1282.68  6521.6 1290.22  6614.4 1296.52  6649.6  1295.6
  6721.6 1299.55  6763.2 1298.39    6856 1305.04    6984 1316.69  6987.2 1318.59
#Mann= 3 ,-1 , 0
  4363.3     .05       0  4944.9     .03       0  5012.6     .05       0
Bank Sta=4944.9,5012.6
XS Rating Curve= 0 ,0
Exp/Cntr=0.3,0.1

Type RM Length L Ch R = 1 ,28975   ,725,725,725
BEGIN DESCRIPTION:
Mapping XS e1c52f34
END DESCRIPTION:
XS GIS Cut Line= 4
      2792032.85     10149235.68      2793393.99     10149325.96
      2794331.49     10149117.63        2795335.     10149145.41
#Sta/Elev= 30
  2898.4 1296.98  3492.5 1277.06  3582.7 1275.44  3933.5 1274.74    4164 1271.77
  4244.2 1272.84  4417.9  1267.6  4551.1 1256.06  4668.2 1256.82  4803.9 1251.79
  4852.6  1253.8  4878.9 1250.33  4950.6 1251.81  4959.4 1250.08  4960.9 1249.08
  5027.4 1250.08  5031.9 1261.06  5053.1 1266.69  5119.8  1270.3  5186.2 1272.47
  5269.5 1271.37  5457.2 1279.76  5477.2 1283.64  5547.2 1290.19  5647.3 1295.31
  5747.3 1302.93  5917.4 1310.36  5962.8 1308.79  6097.4 1318.87  6226.8 1321.74
#Mann= 5 ,-1 , 0
  2898.4     .05       0  4959.4     .05       0  5027.4     .05       0
  5119.8     .12       0  5269.5     .05       0
Bank Sta=4959.4,5027.4
XS Rating Curve= 0 ,0
Exp/Cntr=0.3,0.1

Type RM Length L Ch R = 1 ,28250   ,706,706,706
BEGIN DESCRIPTION:
Mapping XS 070ae958
END DESCRIPTION:
XS GIS Cut Line= 3
      2792309.98     10149440.73      2794086.05     10149867.82
      2794940.21     10149680.32
#Sta/Elev= 30
  3436.7 1288.42  3599.3 1285.65  3934.9 1273.48  4090.5 1269.76    4286 1266.46
  4522.5 1269.01  4794.6 1263.07  4883.7 1259.86  4925.6 1256.06  4967.6 1247.58
  4970.4 1242.72  4971.9 1241.72  5038.4 1242.72  5051.5 1243.87  5077.9 1250.05
  5141.8 1251.44  5170.5 1255.49  5201.2 1262.97  5232.2 1266.27  5273.3 1264.45
  5303.8 1265.16  5314.2 1263.23  5365.4 1266.96    5484 1268.44  5543.2 1270.39
  5679.7 1278.77  5962.3 1285.31    5970 1285.43  6092.3 1286.79  6137.9 1289.39
#Mann= 8 ,-1 , 0
  3436.7     .05       0  4970.4     .05       0  5038.4     .05       0
  5141.8     .05       0  5201.2     .12       0    5484     .05       0
  5962.3     .12       0    5970     .05       0
Bank Sta=4970.4,5038.4
XS Rating Curve= 0 ,0
Exp/Cntr=0.3,0.1

Type RM Length L Ch R = 1 ,27544   ,412,412,412
BEGIN DESCRIPTION:
CRABAPPLE CREEK 41.0
END DESCRIPTION:
XS GIS Cut Line= 3
      2792533.97     10149638.65      2793721.47     10150534.49
      2794402.21     10150913.83
#Sta/Elev= 30
  3690.3 1282.44  3837.7 1279.77    3923 1279.65    4202 1268.98  4416.4 1262.99
  4616.2 1261.22  4701.6 1262.09  4730.7 1260.55  4772.3 1260.44    4816 1257.62
  4907.7 1248.85  4945.1 1246.74  4957.6 1244.45  4980.5 1243.05  4981.8 1241.97
  4983.3 1240.97  5048.4 1240.97  5049.9 1241.97  5051.3 1248.09  5057.8 1249.61
  5151.2 1256.66  5232.5 1260.11  5297.1  1263.9  5315.7 1263.99    5436 1268.22
  5503.2 1272.68  5673.7 1277.05  5776.6 1282.23  5869.5 1290.24  5957.1 1294.73
#Mann= 5 ,-1 , 0
  3690.3     .05       0  4981.8     .05       0  5049.9     .05       0
  5232.5     .12       0  5315.7     .05       0
Bank Sta=4981.8,5049.9
XS Rating Curve= 0 ,0
Exp/Cntr=0.3,0.1

Type RM Length L Ch R = 1 ,27132   ,565,565,565
BEGIN DESCRIPTION:
CRABAPPLE CREEK 40.0
END DESCRIPTION:
XS GIS Cut Line= 3
      2792505.69     10150003.12      2793532.72     10150932.08
      2794435.04     10151305.33
#Sta/Elev= 30
  3866.5 1287.11  3944.6 1284.32  4085.8 1275.47    4298 1264.84  4460.9 1260.88
  4581.2  1260.8  4652.2 1259.02  4744.1 1259.52  4794.2 1252.96  4857.7 1247.39
  4892.8 1242.03  4914.5 1241.47  4942.9 1242.76  4949.6 1244.63  4963.8 1245.21
    4978 1243.09  4979.1 1240.84  4980.6 1239.84  5045.7 1239.84  5047.2 1240.84
    5049 1250.43    5134 1259.09  5226.1 1261.59  5346.1 1268.69  5553.5 1268.15
  5698.2 1271.49  5742.5 1274.19  5990.4 1282.95  6156.6 1292.25  6227.8 1298.03
#Mann= 3 ,-1 , 0
  3866.5     .05       0  4979.1     .05       0  5047.2     .05       0
Bank Sta=4979.1,5047.2
XS Rating Curve= 0 ,0
Exp/Cntr=0.3,0.1

Type RM Length L Ch R = 1 ,26567   ,916,916,916
BEGIN DESCRIPTION:
Mapping XS 1cb0e3af
END DESCRIPTION:
XS GIS Cut Line= 4
      2791742.31     10150404.28      2792648.55     10150716.78
      2793044.39     10151284.49      2794346.52     10151425.12
#Sta/Elev= 30
  3718.8 1280.99  4004.7 1267.43    4209 1261.51  4304.2 1261.58  4561.1 1257.47
    4722 1259.83  4817.1 1259.05  4852.8 1260.31  4966.3 1247.87    4975 1246.25
  4976.7 1239.82  4978.2 1238.82  5043.3 1238.82  5044.8 1239.82  5046.5 1241.88
  5118.1    1242  5147.8 1249.06  5225.4 1256.69  5269.9 1253.13  5296.9 1253.08
  5431.1 1260.87  5642.4 1267.99  5903.9 1266.06  6144.3 1269.88  6246.2 1273.91
  6306.2 1277.59    6333 1280.56  6457.1 1287.21  6567.7 1291.65  6679.2 1294.34
#Mann= 3 ,-1 , 0
  3718.8     .05       0  4976.7     .05       0  5044.8     .05       0
Bank Sta=4976.7,5044.8
XS Rating Curve= 0 ,0
Exp/Cntr=0.3,0.1

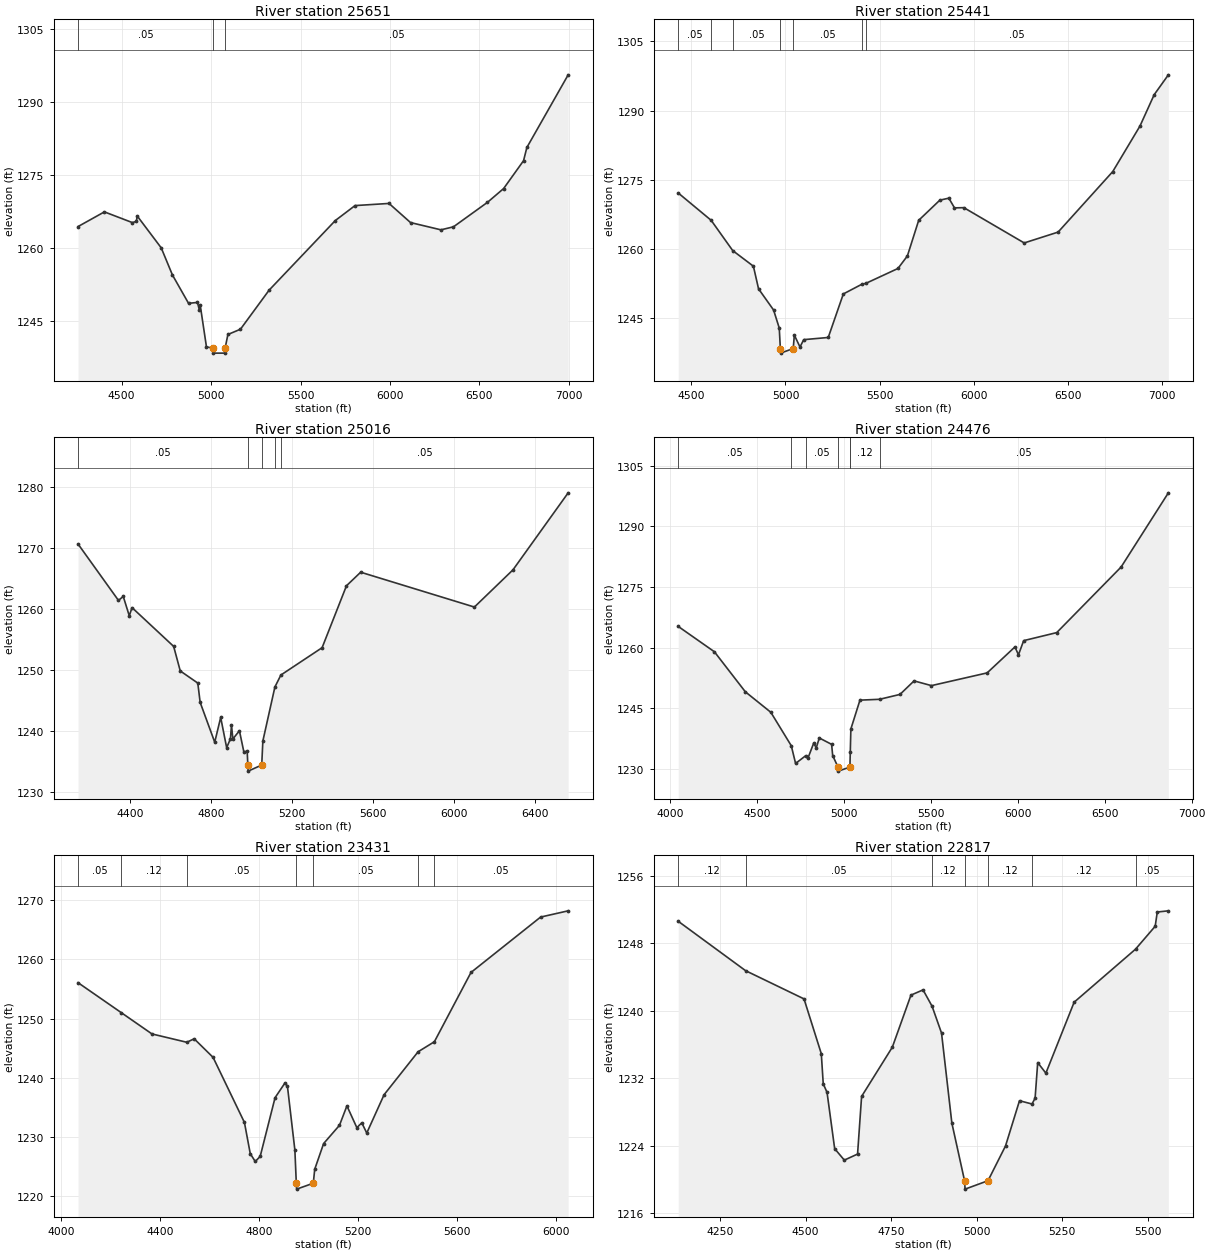
Type RM Length L Ch R = 1 ,25651   ,210,210,210
BEGIN DESCRIPTION:
CRABAPPLE CREEK 39.0
END DESCRIPTION:
XS GIS Cut Line= 3
      2791533.95       10151847.      2791994.87     10151613.63
      2794216.31     10151539.69
#Sta/Elev= 30
  4256.7 1264.44    4404 1267.45  4559.9 1265.26  4582.2 1265.48  4587.8 1266.59
  4721.5 1260.08  4784.1 1254.53  4874.2 1248.71  4924.2 1248.89  4934.2 1247.41
  4939.2 1248.41  4974.3  1239.8    5010  1239.5  5011.5  1238.5    5077  1238.5
  5078.5  1239.5  5094.3 1242.32  5164.4  1243.4  5324.4  1251.4  5694.7 1265.68
  5804.7 1268.74  5994.8 1269.18  6114.9 1265.26    6285 1263.77    6355 1264.39
  6545.1 1269.41  6635.2 1272.23  6746.6 1277.94  6765.2 1280.65    6996 1295.54
#Mann= 3 ,-1 , 0
  4256.7     .05       0    5010     .03       0  5078.5     .05       0
Bank Sta=5010,5078.5
XS Rating Curve= 0 ,0
Exp/Cntr=0.3,0.1

Type RM Length L Ch R = 1 ,25441   ,425,425,425
BEGIN DESCRIPTION:
CRABAPPLE CREEK 38.0
END DESCRIPTION:
XS GIS Cut Line= 3
      2791655.71      10152003.1      2792013.03     10151815.04
      2794210.89     10151732.41
#Sta/Elev= 30
  4430.4 1272.15  4605.3 1266.23  4719.6 1259.68  4829.6 1256.29  4856.9 1251.39
  4936.9 1246.79  4966.9 1242.89  4972.7 1238.46  4974.2 1237.46  5041.2 1238.46
    5047 1241.36    5077 1238.79    5097 1240.38  5227.1 1240.85  5307.2 1250.28
  5404.6 1252.36  5427.3 1252.58  5597.4  1255.8  5647.4 1258.51  5707.5 1266.23
  5819.8  1270.6  5867.6 1271.03  5897.6 1268.93  5947.6 1268.97  6267.9 1261.33
    6448 1263.68  6738.2 1276.79  6882.6 1286.64  6958.3 1293.45  7033.6 1297.75
#Mann= 7 ,-1 , 0
  4430.4     .05       0  4605.3     .12       0  4719.6     .05       0
  4972.7     .05       0  5041.2     .05       0  5404.6     .12       0
  5427.3     .05       0
Bank Sta=4972.7,5041.2
XS Rating Curve= 0 ,0
Exp/Cntr=0.3,0.1

Type RM Length L Ch R = 1 ,25016   ,540,540,540
BEGIN DESCRIPTION:
CRABAPPLE CREEK 37.0
END DESCRIPTION:
XS GIS Cut Line= 3
      2791669.39     10152425.11      2792747.51      10151982.4
      2793997.51     10151914.69
#Sta/Elev= 30
    4145 1270.58  4344.3 1261.34    4368 1261.99  4397.7 1258.81  4411.2 1260.16
  4616.6  1253.8  4649.1 1249.78  4735.6 1247.79  4747.2 1244.63  4819.1  1238.1
  4848.5 1242.16  4877.9 1237.21  4896.4 1238.64  4901.8  1240.9  4908.5 1238.63
  4940.9 1239.98  4962.6 1236.54  4979.2  1236.6  4982.4 1234.36  4983.9 1233.36
  5050.9 1234.36  5056.5  1238.3  5115.9 1247.15  5145.4 1249.11  5348.7 1253.59
  5468.9 1263.74    5539 1265.96  6099.8 1260.25  6290.1 1266.35  6562.3 1278.97
#Mann= 5 ,-1 , 0
    4145     .05       0  4982.4     .05       0  5050.9     .05       0
  5115.9     .12       0  5145.4     .05       0
Bank Sta=4982.4,5050.9
XS Rating Curve= 0 ,0
Exp/Cntr=0.3,0.1

Type RM Length L Ch R = 1 ,24476   ,1045,1045,1045
BEGIN DESCRIPTION:
CRABAPPLE CREEK 36.0
END DESCRIPTION:
XS GIS Cut Line= 3
      2791856.91     10152815.73      2793095.42     10152436.97
      2794617.34     10152425.11
#Sta/Elev= 30
    4049 1265.22  4256.9 1258.94  4434.6 1249.03    4581 1243.96  4698.7 1235.67
  4723.5 1231.28  4781.6  1233.2  4794.3 1232.57  4827.1 1236.27  4842.5 1235.19
  4859.8 1237.59  4930.6 1236.01  4936.6 1233.25  4967.2 1230.38  4968.7 1229.38
  5035.7 1230.38  5037.9 1234.16  5041.2 1239.82  5093.4 1246.96    5206 1247.17
  5323.5 1248.38  5404.4 1251.73  5504.4 1250.56  5824.4 1253.71  5984.4 1260.15
  6004.4 1258.18  6034.4  1261.7  6224.4 1263.69  6594.4 1279.93  6866.1 1298.31
#Mann= 7 ,-1 , 0
    4049     .05       0  4698.7     .12       0  4781.6     .05       0
  4967.2     .05       0  5035.7     .05       0  5037.9     .12       0
    5206     .05       0
Bank Sta=4967.2,5035.7
XS Rating Curve= 0 ,0
Exp/Cntr=0.3,0.1

Type RM Length L Ch R = 1 ,23431   ,614,614,614
BEGIN DESCRIPTION:
CRABAPPLE CREEK 35.0
END DESCRIPTION:
XS GIS Cut Line= 4
      2791919.39     10153138.66      2792225.73     10153501.91
       2793141.5     10153530.61      2793726.72      10153482.4
#Sta/Elev= 30
    4069 1256.07  4243.1 1251.01  4367.4 1247.39  4508.1 1245.98  4537.8 1246.57
  4614.2 1243.42  4740.7  1232.4  4764.2 1227.12  4784.3 1225.79  4804.3 1226.65
  4864.3 1236.59  4904.3 1239.09  4914.3 1238.53  4944.3 1227.74  4950.1 1222.11
  4951.6 1221.11  5018.7 1222.11  5024.4 1224.47  5060.4 1228.83  5124.4 1231.92
  5154.4 1235.21  5194.5 1231.52  5214.5 1232.34  5234.5 1230.61  5304.5  1237.1
  5441.7 1244.37  5507.5 1246.07  5655.2  1257.8  5936.2 1267.18  6047.6 1268.24
#Mann= 7 ,-1 , 0
    4069     .05       0  4243.1     .12       0  4508.1     .05       0
  4950.1     .05       0  5018.7     .05       0  5441.7     .12       0
  5507.5     .05       0
Bank Sta=4950.1,5018.7
XS Rating Curve= 0 ,0
Exp/Cntr=0.3,0.1

Type RM Length L Ch R = 1 ,22817   ,1196,1196,1196
BEGIN DESCRIPTION:
CRABAPPLE CREEK 34.0
END DESCRIPTION:
XS GIS Cut Line= 3
      2792005.69     10154503.11        2792788.       10154117.
      2793305.66     10153903.12
#Sta/Elev= 30
  4127.6 1250.62  4324.4 1244.76  4495.2 1241.41  4545.7 1234.91  4551.4 1231.33
  4562.5 1230.32  4584.8 1223.64    4613 1222.28  4651.7    1223  4663.5 1229.84
  4753.3 1235.68  4807.8 1241.86  4843.1 1242.48  4869.5 1240.54  4897.1 1237.36
  4927.3 1226.68  4964.4 1219.84  4965.9 1218.84    5033 1219.84  5084.1 1223.96
    5125 1229.33  5161.5 1228.94  5170.6 1229.63  5178.2 1233.85  5202.1  1232.6
  5284.7 1241.02  5464.1 1247.31  5521.6 1250.03  5527.7 1251.72  5560.1 1251.86
#Mann= 7 ,-1 , 0
  4127.6     .12       0  4324.4     .05       0  4869.5     .12       0
  4964.4     .07       0    5033     .12       0  5161.5     .12       0
  5464.1     .05       0
Bank Sta=4964.4,5033
XS Rating Curve= 0 ,0
Exp/Cntr=0.3,0.1

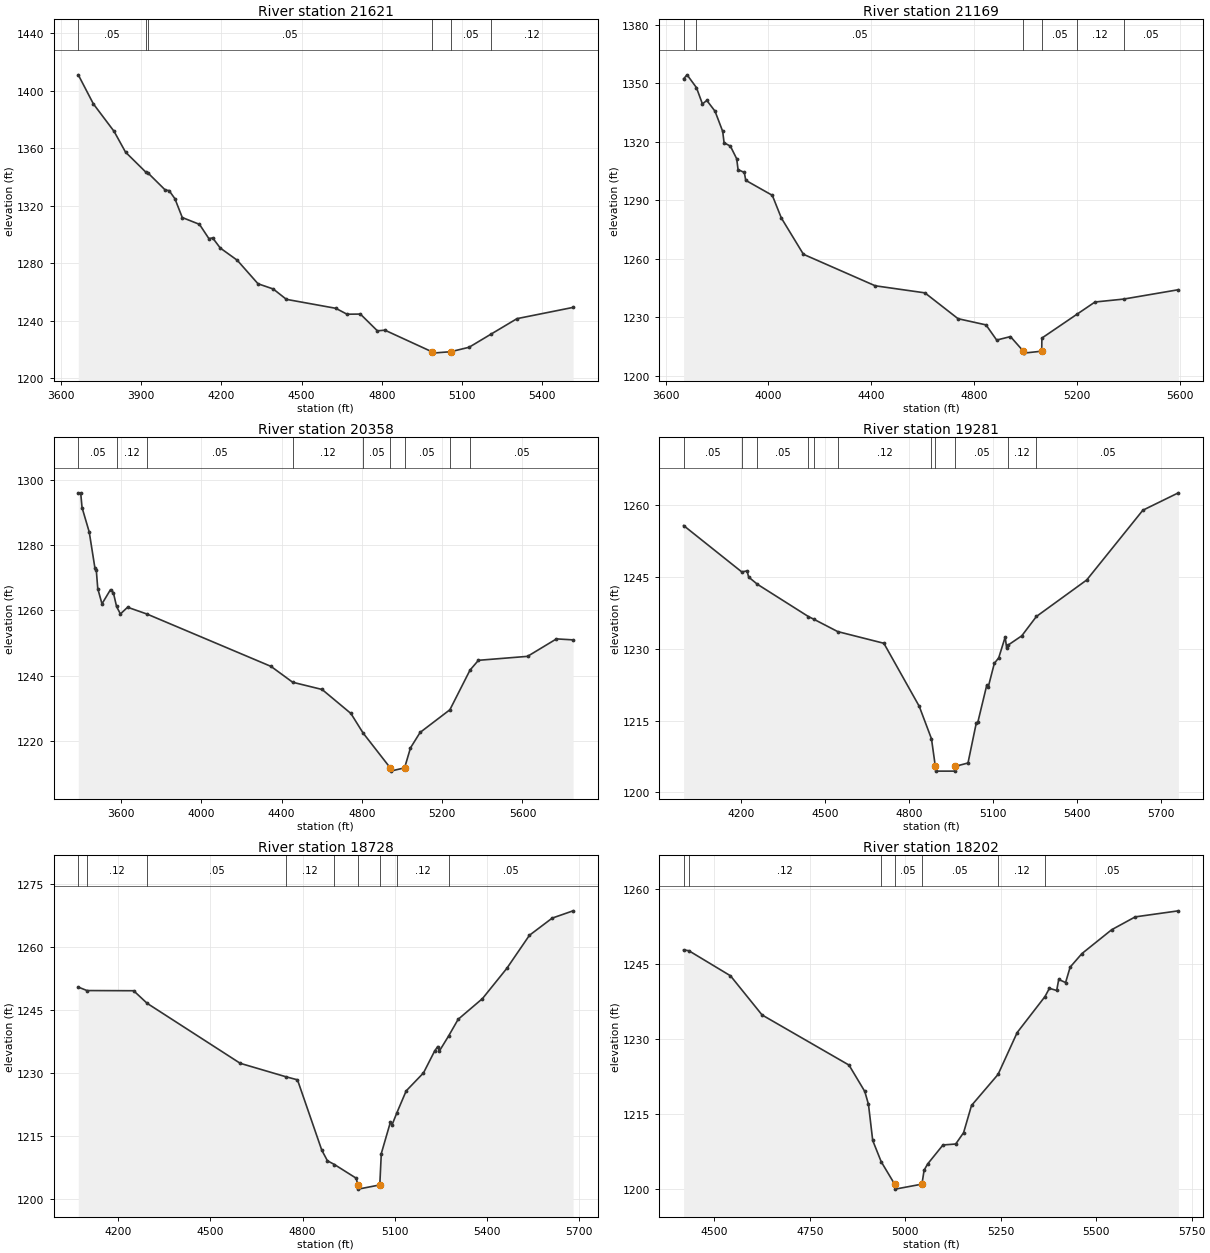
Type RM Length L Ch R = 1 ,21621   ,452,452,452
BEGIN DESCRIPTION:
CRABAPPLE CREEK 32.0
END DESCRIPTION:
XS GIS Cut Line= 3
      2792455.71     10156103.09        2793345.       10155107.
      2793455.68     10154603.11
#Sta/Elev= 30
  3664.7 1411.19  3721.1 1390.98  3798.9 1371.75  3841.5 1357.36  3918.3 1343.27
  3923.9 1343.15  3990.3 1330.94  4004.5 1330.58  4026.2 1324.94  4053.8 1311.82
  4118.2 1307.07  4153.3 1297.16  4167.5 1297.63  4195.9 1290.59  4259.5 1282.07
  4337.2 1265.69  4394.1 1262.07  4443.4 1254.84  4628.2 1248.61  4670.1  1244.5
  4720.1  1244.6  4783.7 1232.95  4812.1 1233.37  4987.2  1218.4  4988.7  1217.4
  5058.6  1218.4  5126.8 1221.48  5208.4 1230.57  5306.1 1241.41  5515.9 1249.24
#Mann= 6 ,-1 , 0
  3664.7     .05       0  3918.3     .12       0  3923.9     .05       0
  4987.2     .05       0  5058.6     .05       0  5208.4     .12       0
Bank Sta=4987.2,5058.6
XS Rating Curve= 0 ,0
Exp/Cntr=0.3,0.1

Type RM Length L Ch R = 1 ,21169   ,811,811,811
BEGIN DESCRIPTION:
CRABAPPLE CREEK 31.0
END DESCRIPTION:
XS GIS Cut Line= 3
      2793294.39      10156477.2      2793869.61     10155003.95
      2793705.67     10154703.08
#Sta/Elev= 30
    3670  1352.2  3683.5 1354.23  3719.9 1347.68  3743.2  1339.3  3760.3  1341.1
  3792.2 1335.57    3822 1325.23  3827.4 1319.39  3851.9 1317.66  3876.4 1311.19
  3881.8 1305.62  3906.2 1304.14  3911.6 1300.12  4014.9 1292.43  4050.1  1280.8
    4136 1262.19  4415.1 1246.04  4608.4 1242.41  4737.3 1229.16    4846 1225.98
  4887.5  1218.2  4941.1 1219.98  4991.3  1212.5  4992.8  1211.5  5062.7  1212.5
  5063.3 1219.21  5199.7 1231.44  5269.9 1237.72  5380.9 1239.21  5594.2 1244.02
#Mann= 6 ,-1 , 0
    3670     .12       0  3719.9     .05       0  4991.3     .05       0
  5062.7     .05       0  5199.7     .12       0  5380.9     .05       0
Bank Sta=4991.3,5062.7
XS Rating Curve= 0 ,0
Exp/Cntr=0.3,0.1

Type RM Length L Ch R = 1 ,20358   ,1077,1077,1077
BEGIN DESCRIPTION:
CRABAPPLE CREEK 30.0
END DESCRIPTION:
XS GIS Cut Line= 3
      2793612.06      10156706.4       2794485.8     10155749.57
      2794763.13     10154612.64
#Sta/Elev= 30
  3386.3 1295.98  3398.3 1295.97  3405.1 1291.47  3440.9 1283.99  3469.2    1273
    3476 1272.39  3483.4  1266.7  3504.4 1262.03  3546.9 1266.38  3561.1 1265.48
  3577.1 1261.22  3596.3 1258.93    3632 1260.99  3728.7 1258.91  4346.8  1242.9
  4454.9 1238.05  4601.5 1235.84  4745.1  1228.5  4805.2 1222.58  4941.1 1211.87
  4942.6 1210.87  5012.6 1211.87    5042 1217.98  5090.1 1222.71  5238.4 1229.64
  5338.6 1241.76  5380.6 1244.76  5625.4 1245.97  5769.5 1251.31  5852.3 1251.01
#Mann= 9 ,-1 , 0
  3386.3     .05       0  3577.1     .12       0  3728.7     .05       0
  4454.9     .12       0  4805.2     .05       0  4941.1     .05       0
  5012.6     .05       0  5238.4     .12       0  5338.6     .05       0
Bank Sta=4941.1,5012.6
XS Rating Curve= 0 ,0
Exp/Cntr=0.3,0.1

Type RM Length L Ch R = 1 ,19281   ,553,553,553
BEGIN DESCRIPTION:
CRABAPPLE CREEK 29.0
END DESCRIPTION:
XS GIS Cut Line= 3
      2794476.65     10156623.04      2795466.17     10156049.12
      2796080.78     10155940.75
#Sta/Elev= 30
  3993.2 1255.72    4201 1246.04  4219.9 1246.25  4225.7 1244.96  4257.1 1243.45
  4439.4 1236.71  4457.6 1236.19  4543.9 1233.58  4708.8 1231.14  4835.2 1217.98
  4878.9  1211.2  4892.7 1205.45  4894.2 1204.45  4962.8 1204.45  4964.3 1205.45
  5009.4 1206.15  5038.9 1214.46  5044.7  1214.7  5076.2 1222.33  5081.9 1222.04
  5103.5 1226.95  5119.2  1228.1  5142.3 1232.45  5147.4 1230.17  5152.9 1230.77
  5201.6  1232.7  5253.9 1236.74  5433.5 1244.35  5634.2 1258.92  5761.2 1262.55
#Mann= 11 ,-1 , 0
  3993.2     .05       0    4201     .12       0  4257.1     .05       0
  4439.4     .12       0  4457.6     .05       0  4543.9     .12       0
  4878.9     .05       0  4892.7     .05       0  4964.3     .05       0
  5152.9     .12       0  5253.9     .05       0
Bank Sta=4892.7,4964.3
XS Rating Curve= 0 ,0
Exp/Cntr=0.3,0.1

Type RM Length L Ch R = 1 ,18728   ,526,526,526
BEGIN DESCRIPTION:
CRABAPPLE CREEK 28.0
END DESCRIPTION:
XS GIS Cut Line= 3
      2794539.22     10156826.15      2795720.64      10156592.1
      2796121.56     10156539.82
#Sta/Elev= 30
  4070.9 1250.43  4099.2  1249.6  4250.8 1249.56  4294.7 1246.57  4597.4  1232.3
  4745.1 1229.12  4783.6 1228.37  4862.5 1211.66  4880.9 1209.13  4903.8 1208.23
  4974.6 1204.97  4979.6 1203.38  4981.1 1202.38  5051.2 1203.38  5056.1 1210.84
  5085.8 1218.33  5090.9 1217.63  5106.8 1220.55    5137 1225.74  5193.3 1230.02
  5229.5 1235.22  5239.5 1236.29  5244.6 1235.18  5274.7 1238.77  5305.9 1242.76
  5384.9 1247.68  5463.9 1254.85  5537.8 1262.75  5611.8 1266.83  5679.6 1268.56
#Mann= 9 ,-1 , 0
  4070.9     .05       0  4099.2     .12       0  4294.7     .05       0
  4745.1     .12       0  4903.8     .05       0  4979.6     .05       0
  5051.2     .05       0  5106.8     .12       0  5274.7     .05       0
Bank Sta=4979.6,5051.2
XS Rating Curve= 0 ,0
Exp/Cntr=0.3,0.1

Type RM Length L Ch R = 1 ,18202   ,617,617,617
BEGIN DESCRIPTION:
CRABAPPLE CREEK 27.0
END DESCRIPTION:
XS GIS Cut Line= 3
      2794737.06     10156971.98      2795471.98      10157168.3
      2795971.06     10157362.45
#Sta/Elev= 30
  4419.1 1247.83  4432.9 1247.66  4541.9 1242.65  4624.7 1234.82  4852.4  1224.8
  4893.8 1219.52  4903.4 1216.94  4914.5 1209.73  4936.8 1205.47  4971.9    1201
  4973.4    1200  5043.5    1201  5049.1 1203.78  5058.5 1205.04  5098.6 1208.83
  5131.9 1209.02  5152.6 1211.29  5173.3 1216.72  5242.9 1222.94    5293 1231.31
  5365.9 1238.51  5377.3 1240.14  5396.5 1239.72  5401.8 1241.92  5419.8  1241.3
  5431.7 1244.38  5462.7  1247.1  5540.5 1251.86  5602.2 1254.43  5715.3 1255.64
#Mann= 7 ,-1 , 0
  4419.1     .05       0  4432.9     .12       0  4936.8     .05       0
  4971.9     .05       0  5043.5     .05       0  5242.9     .12       0
  5365.9     .05       0
Bank Sta=4971.9,5043.5
XS Rating Curve= 0 ,0
Exp/Cntr=0.3,0.1

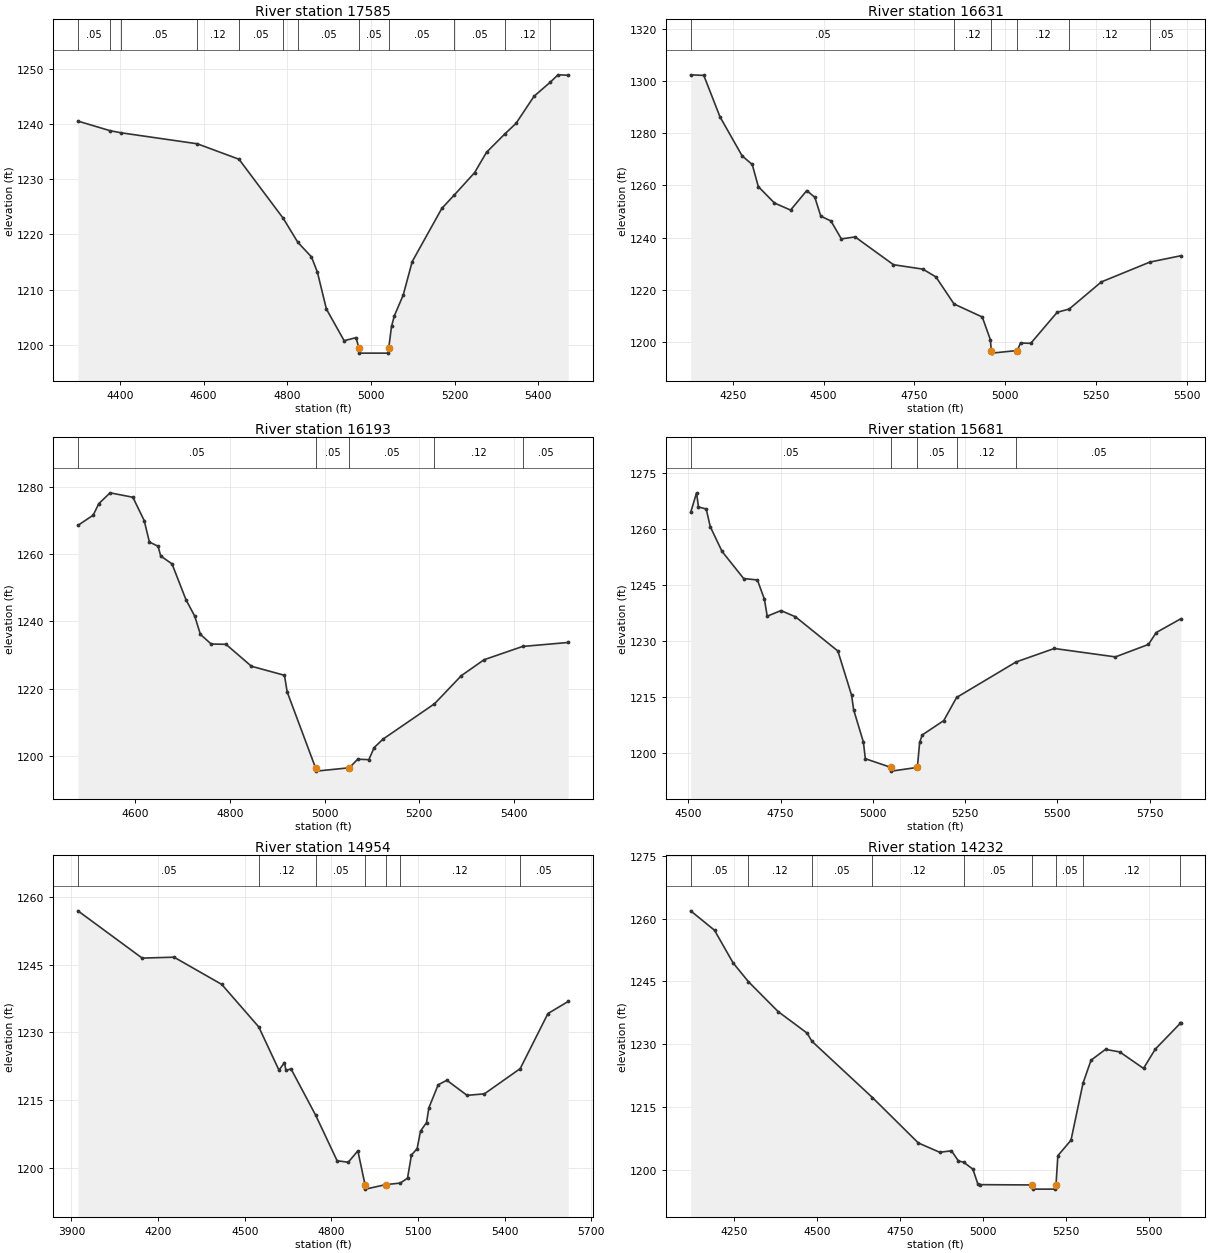
Type RM Length L Ch R = 1 ,17585   ,954,954,954
BEGIN DESCRIPTION:
CRABAPPLE CREEK 26.0
END DESCRIPTION:
XS GIS Cut Line= 3
      2794492.31     10157096.99      2795075.48      10157717.3
      2795324.55     10157919.02
#Sta/Elev= 30
  4299.6 1240.55  4376.9  1238.8  4403.5 1238.42  4584.8 1236.44  4684.7 1233.63
  4790.3 1222.93  4825.3 1218.57  4857.9 1215.93  4872.1 1213.15  4893.6 1206.47
    4936 1200.73  4964.4 1201.29  4971.1 1199.48  4972.6 1198.48  5041.2 1198.48
  5042.7 1199.48  5049.2 1203.32  5056.2 1205.29  5077.2 1209.01  5098.7 1215.08
  5169.4 1224.71  5199.3 1227.15  5247.7 1231.19  5276.4  1234.9  5320.6 1238.26
  5346.8 1240.13    5390 1245.06  5428.7  1247.6  5447.2 1248.94  5471.5 1248.87
#Mann= 12 ,-1 , 0
  4299.6     .05       0  4376.9     .12       0  4403.5     .05       0
  4584.8     .12       0  4684.7     .05       0  4790.3     .12       0
  4825.3     .05       0  4971.1     .05       0  5042.7     .05       0
  5199.3     .05       0  5320.6     .12       0  5428.7     .05       0
Bank Sta=4971.1,5042.7
XS Rating Curve= 0 ,0
Exp/Cntr=0.3,0.1

Type RM Length L Ch R = 1 ,16631   ,438,438,438
BEGIN DESCRIPTION:
CRABAPPLE CREEK 25.0
END DESCRIPTION:
XS GIS Cut Line= 3
      2793555.64     10157903.09      2794601.68     10158435.53
      2794777.37     10158457.48
#Sta/Elev= 30
  4133.7 1302.38  4169.9 1302.16  4214.4  1286.3  4275.5  1271.3  4303.4    1268
    4320 1259.55  4364.5 1253.23    4409 1250.53  4453.5 1257.99  4475.7 1255.46
  4492.3 1248.18  4520.2 1246.35  4548.9 1239.48  4586.9 1240.23  4692.5 1229.58
  4773.3 1227.89  4809.4 1224.91  4859.4 1214.52  4937.2 1209.53  4959.5 1200.82
  4961.9 1196.68  4963.4 1195.68  5033.6 1196.68  5042.6 1199.58  5070.7 1199.43
  5143.6 1211.34  5176.7 1212.59  5265.3 1222.98  5398.9 1230.58  5484.5 1233.02
#Mann= 6 ,-1 , 0
  4133.7     .05       0  4859.4     .12       0  4961.9     .07       0
  5033.6     .12       0  5176.7     .12       0  5398.9     .05       0
Bank Sta=4961.9,5033.6
XS Rating Curve= 0 ,0
Exp/Cntr=0.3,0.1

Type RM Length L Ch R = 1 ,16193   ,512,512,512
BEGIN DESCRIPTION:
CRABAPPLE CREEK 24.0
END DESCRIPTION:
XS GIS Cut Line= 3
      2793605.72     10158453.13      2794455.85     10158800.11
      2794547.35     10158876.33
#Sta/Elev= 30
  4478.2 1268.54  4510.6  1271.6  4522.3    1275  4546.3 1278.22  4594.4 1276.91
  4618.4 1269.99  4629.4 1263.61  4647.9 1262.33  4653.3 1259.46  4677.3  1257.1
  4706.7  1246.5  4725.4 1241.55  4737.4 1236.15  4760.2 1233.29  4791.4 1233.21
  4845.4 1226.68  4915.2    1224    4921 1219.05  4980.9 1196.52  4982.4 1195.52
  5052.6 1196.52  5070.2 1199.06  5093.8 1198.93    5105 1202.52  5123.7 1205.03
  5232.6 1215.52  5289.4 1223.88  5337.5 1228.62  5419.1 1232.57  5515.5 1233.75
#Mann= 5 ,-1 , 0
  4478.2     .05       0  4980.9     .05       0  5052.6     .05       0
  5232.6     .12       0  5419.1     .05       0
Bank Sta=4980.9,5052.6
XS Rating Curve= 0 ,0
Exp/Cntr=0.3,0.1

Type RM Length L Ch R = 1 ,15681   ,727,727,727
BEGIN DESCRIPTION:
CRABAPPLE CREEK 23.0
END DESCRIPTION:
XS GIS Cut Line= 3
       2793405.7     10158953.12       2794054.8     10159164.69
       2794669.4     10159362.62
#Sta/Elev= 30
  4506.3 1264.48  4522.2 1269.73  4527.5 1265.94  4548.4 1265.42  4559.4 1260.68
  4591.3 1254.06  4649.9  1246.8  4687.1 1246.42  4706.1 1241.28  4713.7 1236.73
  4750.9 1238.23  4790.3 1236.57  4905.2 1227.41  4942.3  1215.6    4948 1211.66
  4974.3 1203.07  4979.6  1198.6  5048.9 1196.28  5050.4 1195.28  5120.6 1196.28
  5126.8 1202.99  5133.8 1204.96  5192.1  1208.8  5226.9 1214.99  5388.4  1224.5
  5491.6 1228.09  5657.2 1225.84  5746.7 1229.17  5767.8 1232.35  5834.7 1236.05
#Mann= 5 ,-1 , 0
  4506.3     .05       0  5048.9     .05       0  5120.6     .05       0
  5226.9     .12       0  5388.4     .05       0
Bank Sta=5048.9,5120.6
XS Rating Curve= 0 ,0
Exp/Cntr=0.3,0.1

Type RM Length L Ch R = 1 ,14954   ,722,722,722
BEGIN DESCRIPTION:
CRABAPPLE CREEK 22.0
END DESCRIPTION:
XS GIS Cut Line= 3
      2793007.94     10159951.15       2794174.6      10159607.4
      2794655.63     10159603.11
#Sta/Elev= 30
  3922.4 1256.88  4144.8 1246.43  4255.2 1246.63  4420.4 1240.61  4548.4 1231.22
  4618.5 1221.65  4637.5 1223.33  4642.7 1221.59  4660.2 1221.94  4745.7 1211.67
  4819.8 1201.63  4858.3 1201.29  4891.6 1203.82  4916.3 1196.35  4917.8 1195.35
    4988 1196.35  5038.7 1196.69  5063.5 1197.77  5077.2 1202.91  5096.8 1204.29
  5108.5 1208.18  5129.4 1210.08  5137.4 1213.32  5169.7 1218.42  5199.7 1219.42
  5269.7 1216.08  5329.7 1216.42  5453.6 1221.99  5549.7 1234.17  5619.7 1236.84
#Mann= 7 ,-1 , 0
  3922.4     .05       0  4548.4     .12       0  4745.7     .05       0
  4916.3     .05       0    4988     .05       0  5038.7     .12       0
  5453.6     .05       0
Bank Sta=4916.3,4988
XS Rating Curve= 0 ,0
Exp/Cntr=0.3,0.1

Type RM Length L Ch R = 1 ,14232   ,376,376,376
BEGIN DESCRIPTION:
CRABAPPLE CREEK 21.0
END DESCRIPTION:
XS GIS Cut Line= 3
      2794005.68     10160853.12      2794695.68     10159942.01
      2794897.44     10159676.58
#Sta/Elev= 30
  4119.2 1261.87    4191 1257.23  4247.2  1249.4  4293.3 1244.92  4382.6 1237.79
  4469.7 1232.65  4484.4 1230.69  4666.6 1217.24  4804.7 1206.39  4869.2 1204.16
  4904.6 1204.51  4925.4  1202.1  4941.5 1201.77  4969.1 1200.12  4983.6 1196.67
  4989.9 1196.42  5147.5 1196.35    5149 1195.35  5217.8 1195.35  5219.3 1196.35
    5225 1203.35  5264.5 1207.04  5300.7 1220.67  5324.9 1226.17  5368.5 1228.76
  5411.4 1228.14  5482.9 1224.21  5518.2  1228.8  5594.2 1235.03  5595.5 1235.13
#Mann= 9 ,-1 , 0
  4119.2     .05       0  4293.3     .12       0  4484.4     .05       0
  4666.6     .12       0  4941.5     .05       0  5147.5     .05       0
  5219.3     .05       0  5300.7     .12       0  5594.2     .05       0
Bank Sta=5147.5,5219.3
XS Rating Curve= 0 ,0
Exp/Cntr=0.3,0.1