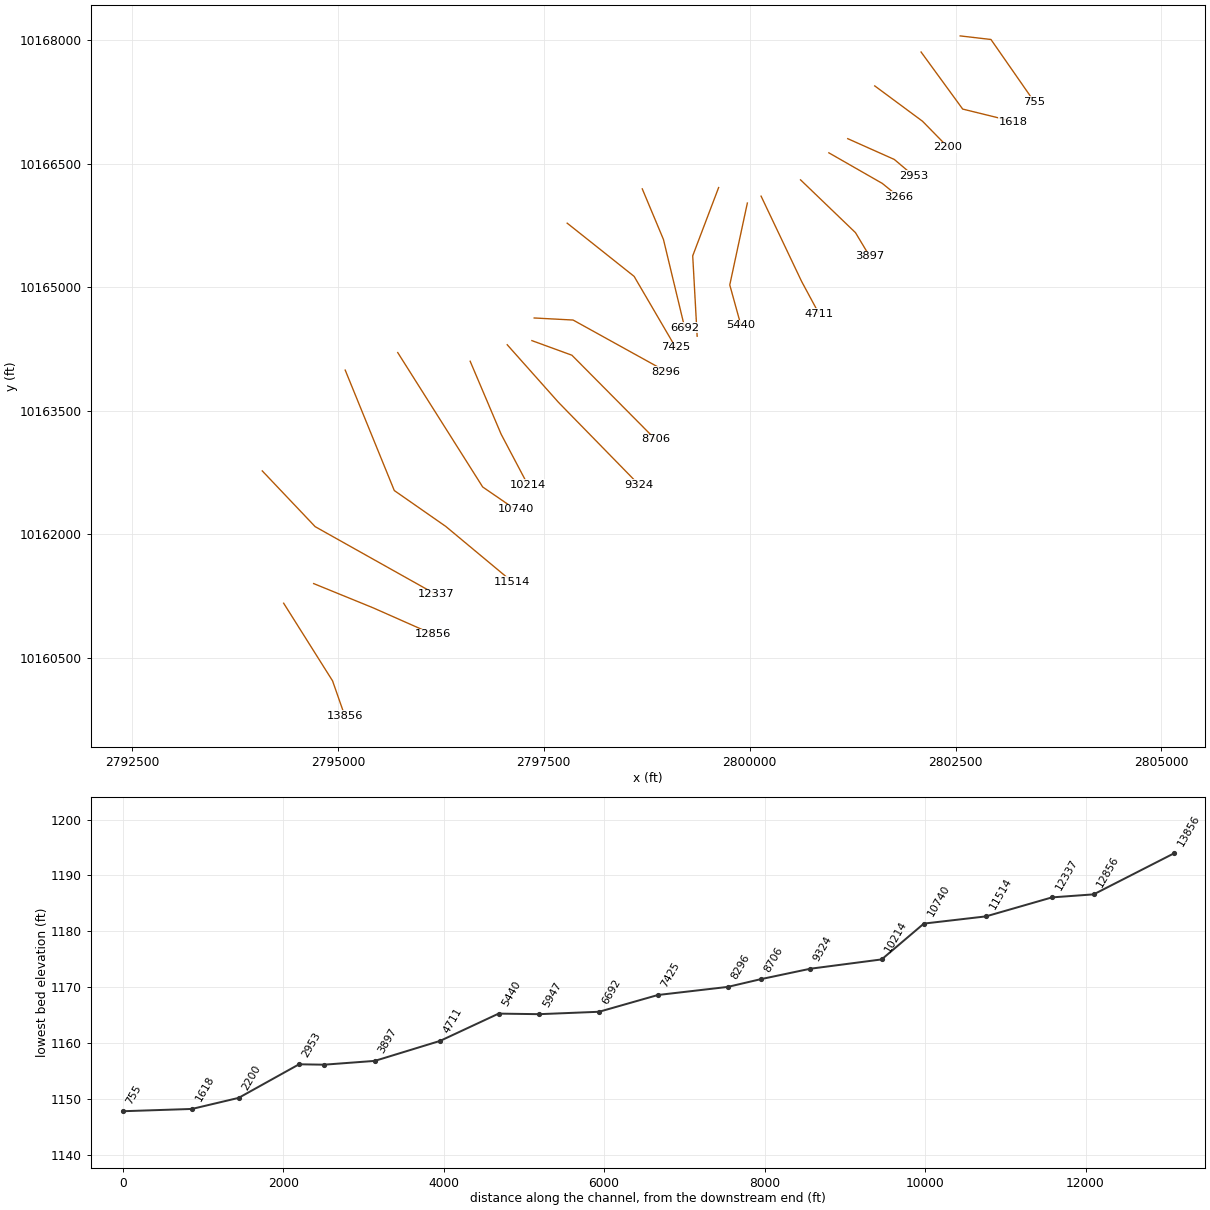
HEC-RAS study CRABAPPLE CREEK.prj: CRABAPPLE CREEK Base Level Engineering

--- CRABAPPLE CREEK.g01 (geometry) --- (continued)

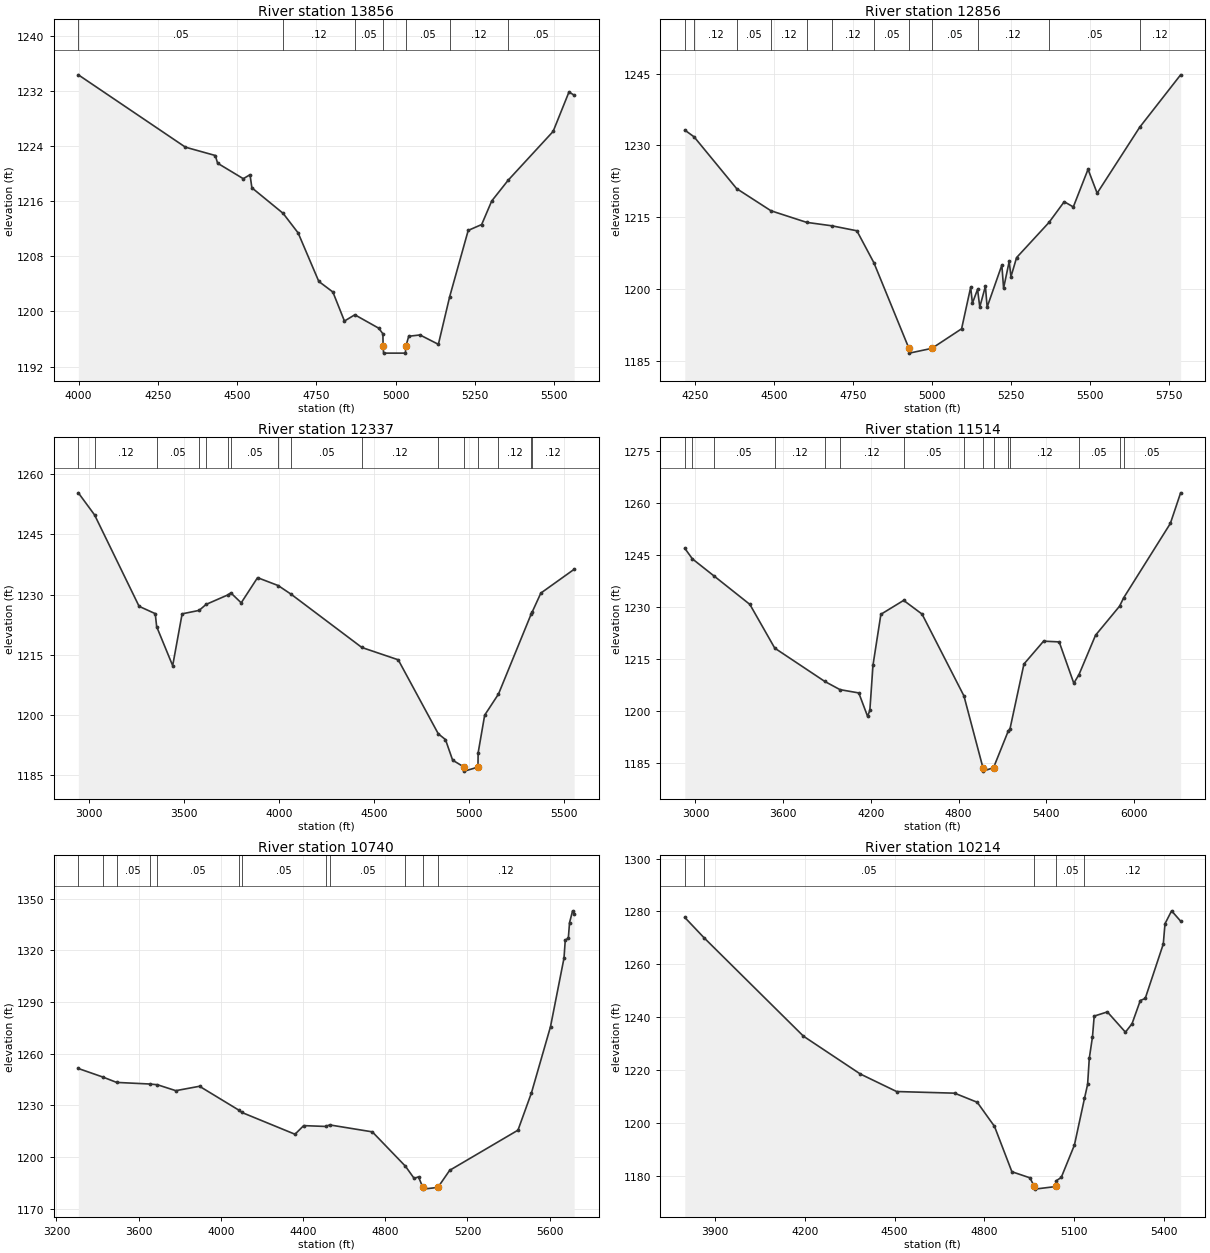
Type RM Length L Ch R = 1 ,13856   ,1000,1000,1000
BEGIN DESCRIPTION:
CRABAPPLE CREEK 20.0
END DESCRIPTION:
XS GIS Cut Line= 3
      2794341.25     10161164.72      2794935.01     10160221.99
      2795083.35     10159797.71
#Sta/Elev= 30
  3999.3 1234.38    4337 1223.87  4431.2 1222.66  4438.5 1221.54  4519.5 1219.29
  4540.7 1219.87  4546.6 1217.97    4645 1214.26  4692.5 1211.41  4757.6 1204.37
    4802 1202.83  4838.5 1198.61  4871.2 1199.52  4946.7 1197.57  4959.8 1196.75
  4960.4 1194.95  4961.9 1193.95  5030.7 1193.95  5032.2 1194.95  5041.2  1196.4
  5076.7 1196.59  5134.7 1195.23  5170.3 1202.14  5228.8 1211.78  5271.2 1212.63
  5302.9 1216.05    5355 1219.08  5496.6 1226.16  5546.6 1231.89  5562.9 1231.42
#Mann= 7 ,-1 , 0
  3999.3     .05       0    4645     .12       0  4871.2     .05       0
  4960.4     .05       0  5032.2     .05       0  5170.3     .12       0
    5355     .05       0
Bank Sta=4960.4,5032.2
XS Rating Curve= 0 ,0
Exp/Cntr=0.3,0.1

Type RM Length L Ch R = 1 ,12856   ,519,519,519
BEGIN DESCRIPTION:
CRABAPPLE CREEK 19.0
END DESCRIPTION:
XS GIS Cut Line= 3
      2794705.65     10161403.12       2795429.5       10161108.
      2796148.59     10160789.68
#Sta/Elev= 30
  4218.3  1233.2  4247.8 1231.78  4382.2 1220.98  4490.8 1216.35  4603.6 1213.93
  4683.4 1213.21  4762.5 1212.17  4816.3  1205.5  4927.1 1187.62  4928.6 1186.62
  4999.8 1187.62  5093.7  1191.7  5122.4 1200.38  5127.9 1197.05  5144.2 1199.94
  5151.2 1196.24    5169 1200.59  5174.5 1196.24    5221    1205  5226.5 1200.18
  5244.3 1205.79  5249.8 1202.57  5267.6 1206.57  5370.2 1213.92  5418.3 1218.24
    5447 1217.15  5493.6 1225.01  5522.4 1220.02  5656.9 1233.79  5786.4 1244.74
#Mann= 12 ,-1 , 0
  4218.3     .05       0  4247.8     .12       0  4382.2     .05       0
  4490.8     .12       0  4603.6     .05       0  4683.4     .12       0
  4816.3     .05       0  4927.1     .03       0  4999.8     .05       0
  5144.2     .12       0  5370.2     .05       0  5656.9     .12       0
Bank Sta=4927.1,4999.8
XS Rating Curve= 0 ,0
Exp/Cntr=0.3,0.1

Type RM Length L Ch R = 1 ,12337   ,823,823,823
BEGIN DESCRIPTION:
CRABAPPLE CREEK 18.0
END DESCRIPTION:
XS GIS Cut Line= 3
      2794081.56     10162771.32      2794723.89     10162094.27
      2796186.59     10161273.94
#Sta/Elev= 30
  2944.4  1255.3    3030  1249.8  3264.3 1227.07  3349.3 1225.25  3356.8 1222.01
  3441.1 1212.31  3490.8  1225.2  3580.4 1226.06  3617.1 1227.55  3730.7 1229.89
  3747.3 1230.41  3801.9 1227.94  3887.9  1234.2  3996.3 1232.24    4064  1230.1
  4437.2 1216.83  4628.5 1213.77  4839.4 1195.36  4877.2 1193.93  4914.9 1188.81
  4975.5 1187.08    4977 1186.08  5048.2 1187.08  5049.2 1190.62  5083.6    1200
  5156.3 1205.25  5327.9 1225.09  5333.5 1225.63  5379.3 1230.36  5554.7 1236.28
#Mann= 16 ,-1 , 0
  2944.4     .05       0    3030     .12       0  3356.8     .05       0
  3580.4     .12       0  3617.1     .05       0  3730.7     .12       0
  3747.3     .05       0  3996.3     .12       0    4064     .05       0
  4437.2     .12       0  4839.4     .05       0  4975.5     .05       0
  5048.2     .05       0  5156.3     .12       0  5327.9     .05       0
  5333.5     .12       0
Bank Sta=4975.5,5048.2
XS Rating Curve= 0 ,0
Exp/Cntr=0.3,0.1

Type RM Length L Ch R = 1 ,11514   ,774,774,774
BEGIN DESCRIPTION:
CRABAPPLE CREEK 17.0
END DESCRIPTION:
XS GIS Cut Line= 4
      2795088.49     10163995.27      2795684.62     10162532.94
      2796310.01     10162096.99      2797117.29     10161425.12
#Sta/Elev= 30
    2927 1246.94  2979.3 1243.88    3124 1239.06  3372.1 1230.76  3542.4 1218.15
  3884.5 1208.55  3988.8 1206.18  4117.2 1205.23  4177.2  1198.5  4192.8 1200.17
  4214.4 1213.26  4268.4 1227.91  4424.1 1231.92  4549.9 1227.97  4836.5 1204.37
  4966.4 1183.68  4967.9 1182.68  5039.1 1183.68  5138.8 1194.16  5151.7  1194.9
    5247 1213.57  5381.3 1220.16  5488.1 1219.95  5588.1 1208.03  5623.7 1210.54
  5736.7 1221.87  5901.3 1230.26  5928.7 1232.63  6248.4  1254.1  6318.8 1262.94
#Mann= 15 ,-1 , 0
    2927     .05       0  2979.3     .12       0    3124     .05       0
  3542.4     .12       0  3884.5     .05       0  3988.8     .12       0
  4424.1     .05       0  4836.5     .12       0  4966.4     .07       0
  5039.1     .12       0  5138.8     .05       0  5151.7     .12       0
  5623.7     .05       0  5901.3     .12       0  5928.7     .05       0
Bank Sta=4966.4,5039.1
XS Rating Curve= 0 ,0
Exp/Cntr=0.3,0.1

Type RM Length L Ch R = 1 ,10740   ,526,526,526
BEGIN DESCRIPTION:
CRABAPPLE CREEK 16.0
END DESCRIPTION:
XS GIS Cut Line= 3
      2795726.52     10164207.95      2796757.93     10162576.15
       2797155.7      10162303.1
#Sta/Elev= 30
  3306.6 1251.39  3426.9 1246.39  3492.8 1243.32  3653.3 1242.39  3691.2 1241.97
    3781 1238.52  3896.3 1241.08  4087.9 1227.21    4102  1225.9  4360.9 1213.24
  4403.3 1218.24  4510.4 1217.76  4529.5 1218.66  4737.3 1214.62  4898.5 1194.67
  4940.8 1187.62    4962 1188.53    4983 1182.39  4984.5 1181.39  5056.4 1182.39
  5113.8 1192.31  5446.1  1215.6  5511.8  1237.3  5604.4 1275.67  5670.1 1315.47
  5676.2  1325.9  5691.1 1326.99  5697.1 1336.06    5712 1342.88  5719.5 1341.21
#Mann= 12 ,-1 , 0
  3306.6     .05       0  3426.9     .12       0  3492.8     .05       0
  3653.3     .12       0  3691.2     .05       0  4087.9     .12       0
    4102     .05       0  4510.4     .12       0  4529.5     .05       0
  4898.5     .12       0    4983     .07       0  5056.4     .12       0
Bank Sta=4983,5056.4
XS Rating Curve= 0 ,0
Exp/Cntr=0.3,0.1

Type RM Length L Ch R = 1 ,10214   ,890,890,890
BEGIN DESCRIPTION:
CRABAPPLE CREEK 15.0
END DESCRIPTION:
XS GIS Cut Line= 3
       2796605.7     10164103.08      2796981.89     10163216.78
      2797305.69      10162603.1
#Sta/Elev= 30
    3799 1277.73    3863 1270.08  4195.6 1232.81  4385.6 1218.51  4506.7 1211.89
  4700.6 1211.27  4776.2 1207.82  4833.8  1198.7  4891.9 1181.56  4952.3 1179.25
  4966.7 1175.98  4968.2 1174.98  5040.1 1175.98  5040.4 1178.17  5056.8 1179.39
  5100.8 1191.63  5134.4 1209.26  5144.9 1214.59  5150.5 1224.44  5161.2 1232.58
  5166.9 1240.42  5210.9    1242  5271.3 1234.34  5293.4 1237.55    5321 1246.31
  5337.4 1247.09  5397.8 1267.69  5403.5 1275.35  5425.5 1280.23  5455.7 1276.33
#Mann= 5 ,-1 , 0
    3799     .12       0    3863     .05       0  4966.7     .05       0
  5040.1     .05       0  5134.4     .12       0
Bank Sta=4966.7,5040.1
XS Rating Curve= 0 ,0
Exp/Cntr=0.3,0.1

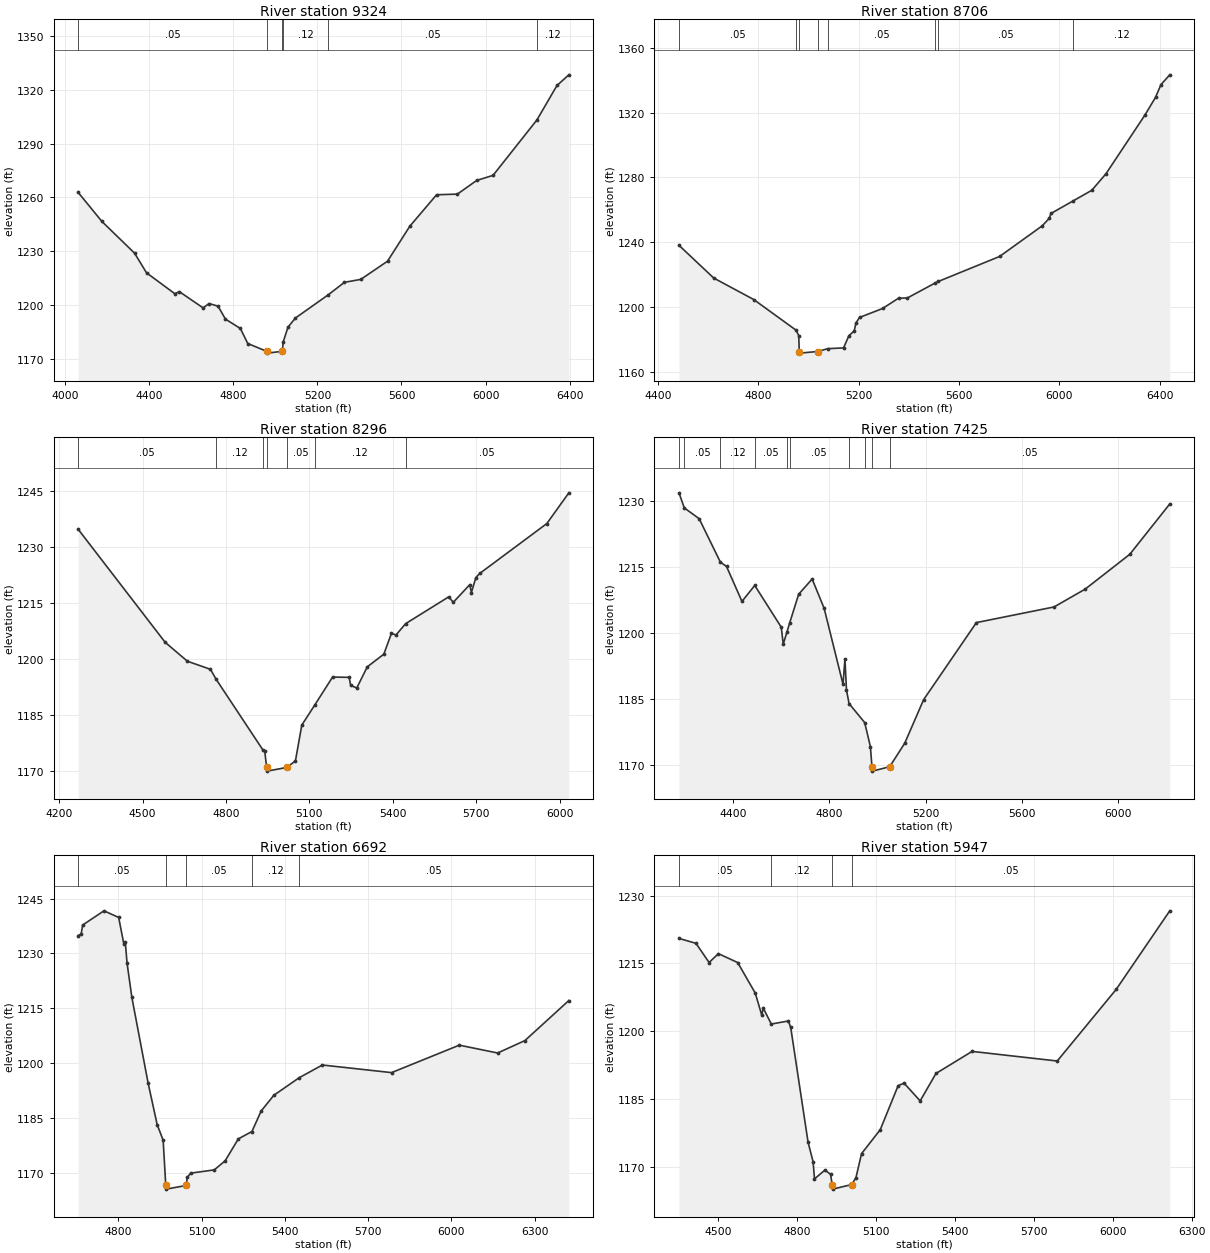
Type RM Length L Ch R = 1 ,9324    ,618,618,618
BEGIN DESCRIPTION:
CRABAPPLE CREEK 14.0
END DESCRIPTION:
XS GIS Cut Line= 3
       2797055.7     10164303.09      2797679.75       10163602.
      2798655.68     10162603.12
#Sta/Elev= 30
  4061.4 1262.86  4174.7 1246.64  4330.2 1228.97  4387.1 1218.04  4521.7  1206.4
  4543.3 1207.54  4656.3  1198.5  4684.7 1200.92  4727.4 1199.45  4762.5 1192.26
  4833.6 1187.03  4868.7 1178.66  4959.2 1174.31  4960.7 1173.31  5032.6 1174.31
  5037.9 1179.74    5060 1187.75  5095.4 1192.85    5251 1205.72  5328.7 1212.73
  5406.4 1214.37  5533.7 1224.49  5639.9 1243.99  5767.2  1261.5  5866.1 1261.85
  5958.1 1269.48  6035.8 1272.29  6244.6 1303.17    6340 1322.34  6396.5 1328.28
#Mann= 6 ,-1 , 0
  4061.4     .05       0  4959.2     .03       0  5032.6     .05       0
  5037.9     .12       0    5251     .05       0  6244.6     .12       0
Bank Sta=4959.2,5032.6
XS Rating Curve= 0 ,0
Exp/Cntr=0.3,0.1

Type RM Length L Ch R = 1 ,8706    ,410,410,410
BEGIN DESCRIPTION:
CRABAPPLE CREEK 13.0
END DESCRIPTION:
XS GIS Cut Line= 3
      2797355.65     10164353.13      2797841.25       10164176.
      2798855.67     10163153.12
#Sta/Elev= 30
  4483.1 1238.06  4621.5 1217.85  4781.2 1204.56    4950 1185.62  4960.7 1182.31
  4962.9 1172.44  4964.4 1171.44  5036.4 1172.44  5076.7  1174.2  5139.5 1174.67
  5160.7 1182.19    5182 1185.16    5189 1190.06  5203.1 1193.48  5295.1 1199.02
  5358.7 1205.37  5394.1 1205.53    5506 1214.87  5517.8 1215.75  5761.8 1231.16
  5931.5 1250.05  5959.8  1254.7  5966.8 1257.73  6055.1 1265.49  6129.5 1272.04
  6186.1 1282.26  6341.6 1318.55  6384.1 1329.56  6405.3 1337.31  6440.6  1343.4
#Mann= 8 ,-1 , 0
  4483.1     .05       0    4950     .12       0  4962.9     .07       0
  5036.4     .12       0  5076.7     .05       0    5506     .12       0
  5517.8     .05       0  6055.1     .12       0
Bank Sta=4962.9,5036.4
XS Rating Curve= 0 ,0
Exp/Cntr=0.3,0.1

Type RM Length L Ch R = 1 ,8296    ,871,871,871
BEGIN DESCRIPTION:
CRABAPPLE CREEK 12.0
END DESCRIPTION:
XS GIS Cut Line= 3
      2797382.97     10164628.23      2797855.68     10164603.11
      2798986.23     10163977.67
#Sta/Elev= 30
  4268.1  1234.8  4581.3 1204.53  4661.4 1199.46  4744.3  1197.3  4764.4 1194.67
  4933.6 1175.65  4939.6 1175.35  4946.4 1171.06  4947.9 1170.06  5019.9 1171.06
    5050 1172.83  5072.9 1182.38  5119.4 1187.74  5183.6 1195.23  5243.1 1195.15
  5248.8 1192.99  5270.6 1192.31  5308.4 1197.96  5367.9 1201.35  5395.4 1206.93
  5411.5 1206.47  5446.4 1209.52  5601.6  1216.7  5617.6 1215.22  5677.2 1219.96
  5682.9 1217.84  5698.9 1221.83  5712.9 1222.95  5954.3  1236.3  6033.5 1244.52
#Mann= 7 ,-1 , 0
  4268.1     .05       0  4764.4     .12       0  4933.6     .05       0
  4946.4     .05       0  5019.9     .05       0  5119.4     .12       0
  5446.4     .05       0
Bank Sta=4946.4,5019.9
XS Rating Curve= 0 ,0
Exp/Cntr=0.3,0.1

Type RM Length L Ch R = 1 ,7425    ,733,733,733
BEGIN DESCRIPTION:
CRABAPPLE CREEK 11.0
END DESCRIPTION:
XS GIS Cut Line= 3
      2797784.01     10165779.25      2798596.47     10165133.44
      2799101.16     10164269.75
#Sta/Elev= 30
  4175.7 1231.94  4197.7 1228.51  4259.4 1226.06  4347.5 1216.18  4373.1 1215.19
  4437.2 1207.23  4490.3 1210.86  4600.6 1201.35  4608.6  1197.5  4624.2 1200.28
  4634.8 1202.23  4672.7 1208.86  4728.7 1212.32  4778.4 1205.68  4856.9 1188.38
  4864.9 1194.16  4871.3 1187.04  4882.1 1183.98  4946.9 1179.66  4970.6  1174.2
  4977.1 1169.61  4978.6 1168.61  5050.7 1169.61  5113.2 1174.96  5191.7 1184.87
  5410.8 1202.41  5733.3 1205.97  5862.5 1210.02  6047.9 1217.95  6213.9 1229.41
#Mann= 10 ,-1 , 0
  4175.7     .12       0  4197.7     .05       0  4347.5     .12       0
  4490.3     .05       0  4624.2     .12       0  4634.8     .05       0
  4882.1     .12       0  4946.9     .05       0  4977.1     .05       0
  5050.7     .05       0
Bank Sta=4977.1,5050.7
XS Rating Curve= 0 ,0
Exp/Cntr=0.3,0.1

Type RM Length L Ch R = 1 ,6692    ,745,745,745
BEGIN DESCRIPTION:
CRABAPPLE CREEK 10.0
END DESCRIPTION:
XS GIS Cut Line= 3
      2798695.41     10166195.99      2798952.88     10165580.98
      2799210.87     10164509.22
#Sta/Elev= 30
  4654.4 1234.88  4665.5 1235.29  4670.9 1237.76  4747.7 1241.64  4800.7 1239.83
  4819.1 1232.67  4824.5 1233.14    4831 1227.33  4848.3 1217.98  4906.9 1194.56
  4939.4 1183.26  4961.1 1178.95  4970.5 1166.61    4972 1165.61  5044.1 1166.61
  5047.8  1168.8  5060.3 1169.97  5145.4 1170.87  5184.6 1173.35  5232.1 1179.34
  5281.1 1181.35  5314.4 1186.96  5360.1 1191.25  5451.5 1196.05  5534.9 1199.52
  5784.4 1197.44  6028.6 1204.94  6166.9  1202.8  6265.2  1206.2  6423.5 1217.14
#Mann= 5 ,-1 , 0
  4654.4     .05       0  4970.5     .03       0  5044.1     .05       0
  5281.1     .12       0  5451.5     .05       0
Bank Sta=4970.5,5044.1
XS Rating Curve= 0 ,0
Exp/Cntr=0.3,0.1

Type RM Length L Ch R = 1 ,5947    ,507,507,507
BEGIN DESCRIPTION:
CRABAPPLE CREEK 9.0
END DESCRIPTION:
XS GIS Cut Line= 3
      2799622.52     10166211.58      2799308.05     10165382.73
      2799361.99     10164406.21
#Sta/Elev= 30
  4352.3 1220.54    4417 1219.45  4466.6 1215.22  4502.1 1217.17  4575.3 1215.21
  4642.1 1208.46  4666.9 1203.57  4672.2 1205.18    4703 1201.63  4767.8 1202.31
  4776.7  1200.9  4842.7 1175.54  4861.8 1171.22  4867.1 1167.44  4906.8 1169.39
  4928.2 1168.44  4934.2 1166.18  4935.7 1165.18  5007.8 1166.18  5024.5 1167.69
  5045.9 1173.02    5117 1178.31  5184.9 1188.03  5207.4 1188.58  5268.5 1184.66
  5328.6 1190.72  5465.8 1195.59  5789.3 1193.47  6013.2 1209.28  6216.8 1226.63
#Mann= 4 ,-1 , 0
  4352.3     .05       0    4703     .12       0  4934.2     .05       0
  5007.8     .05       0
Bank Sta=4934.2,5007.8
XS Rating Curve= 0 ,0
Exp/Cntr=0.3,0.1

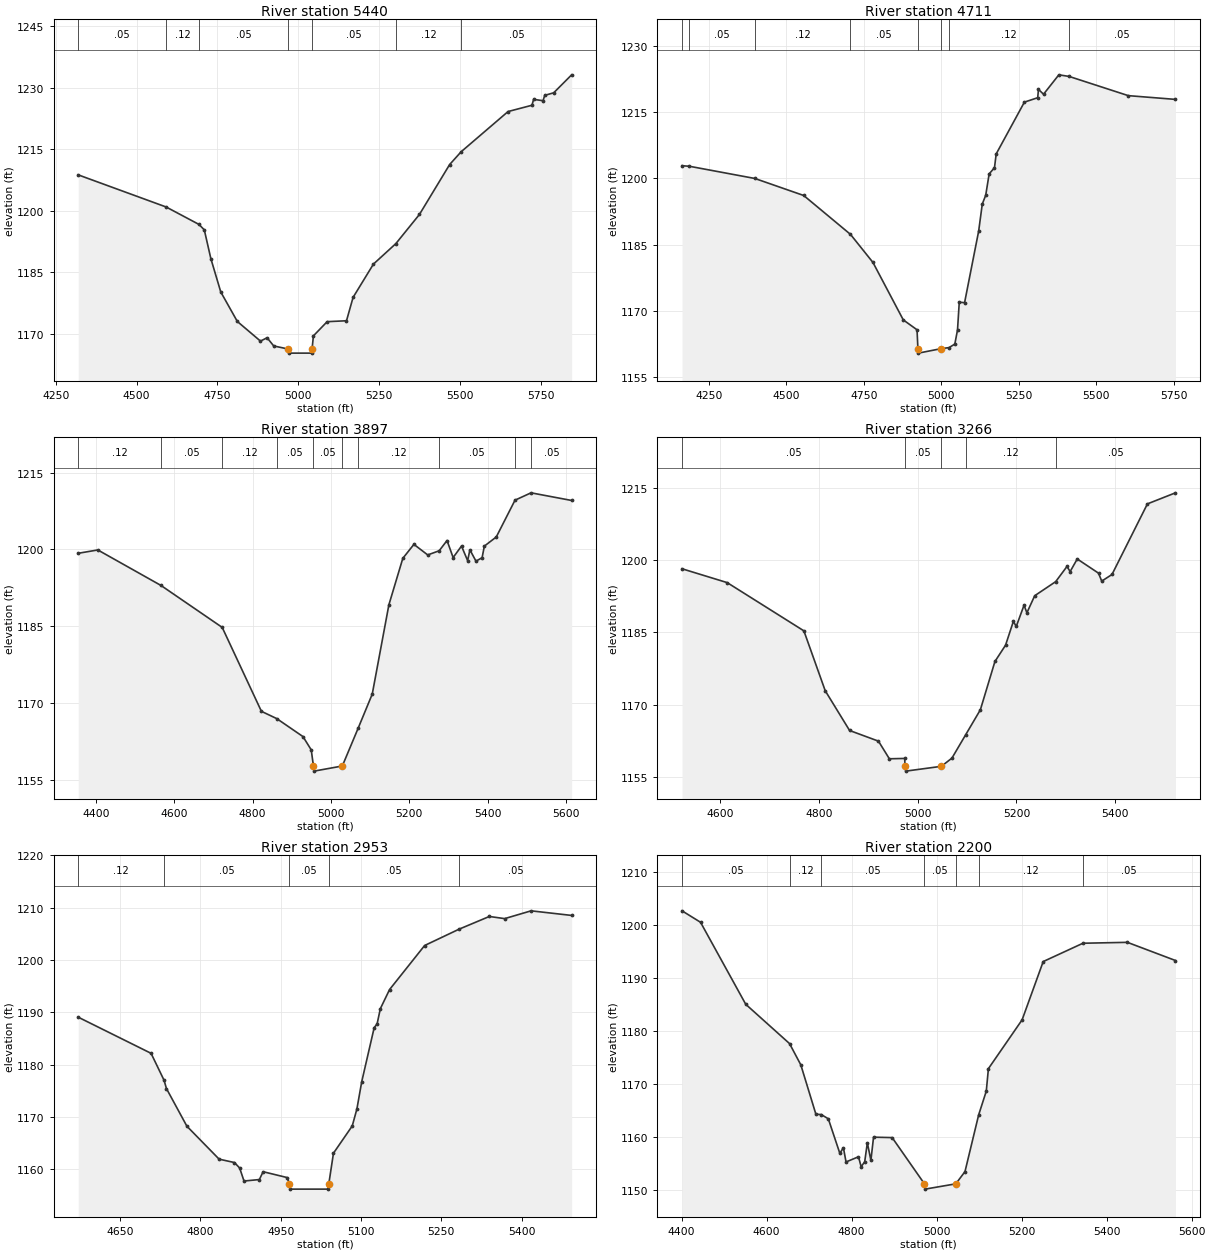
Type RM Length L Ch R = 1 ,5440    ,729,729,729
BEGIN DESCRIPTION:
CRABAPPLE CREEK 8.0
END DESCRIPTION:
XS GIS Cut Line= 3
      2799971.46     10166024.03      2799757.93     10165029.28
      2799893.35     10164539.67
#Sta/Elev= 30
  4319.6 1208.74  4591.4 1200.91  4692.9 1196.66  4709.4 1195.33  4729.7 1188.31
  4760.3 1180.19  4811.5    1173  4883.1 1168.21  4903.5 1169.03    4924 1167.03
    4969 1166.28  4970.5 1165.28  5041.1 1165.28  5042.6 1166.28  5046.7 1169.49
  5089.2 1172.95    5149 1173.17  5169.4 1178.88  5232.3 1186.99  5301.7 1191.99
  5374.5 1199.09  5467.9 1211.26  5503.5 1214.38  5648.5 1224.18  5722.3 1225.71
  5727.5 1227.15  5756.6 1226.82  5761.8 1228.12  5789.6 1228.75    5845 1233.13
#Mann= 7 ,-1 , 0
  4319.6     .05       0  4591.4     .12       0  4692.9     .05       0
    4969     .05       0  5042.6     .05       0  5301.7     .12       0
  5503.5     .05       0
Bank Sta=4969,5042.6
XS Rating Curve= 0 ,0
Exp/Cntr=0.3,0.1

Type RM Length L Ch R = 1 ,4711    ,814,814,814
BEGIN DESCRIPTION:
CRABAPPLE CREEK 7.0
END DESCRIPTION:
XS GIS Cut Line= 3
      2800138.14     10166107.41      2800630.24     10165071.81
      2800840.97     10164680.86
#Sta/Elev= 30
  4164.1 1202.89  4187.6 1202.77  4398.9    1200  4556.4 1196.14  4707.2 1187.32
  4779.6 1180.96  4877.4 1167.93  4921.7 1165.69  4924.5  1161.4    4926  1160.4
  4998.2  1161.4  5024.8 1161.65  5043.5 1162.45  5052.2 1165.65  5057.8 1171.93
    5075 1171.85  5120.4 1188.08  5132.1 1194.22  5143.1 1196.19  5154.2 1201.04
  5171.4 1202.44  5176.9 1205.57  5267.8 1217.31  5310.7 1218.31  5313.2  1220.2
  5329.5  1219.1  5378.9  1223.5  5411.8 1223.14  5602.8 1218.78  5754.8 1217.93
#Mann= 8 ,-1 , 0
  4164.1     .12       0  4187.6     .05       0  4398.9     .12       0
  4707.2     .05       0  4924.5     .05       0  4998.2     .05       0
  5024.8     .12       0  5411.8     .05       0
Bank Sta=4924.5,4998.2
XS Rating Curve= 0 ,0
Exp/Cntr=0.3,0.1

Type RM Length L Ch R = 1 ,3897    ,631,631,631
BEGIN DESCRIPTION:
CRABAPPLE CREEK 6.0
END DESCRIPTION:
XS GIS Cut Line= 3
       2800617.3     10166305.32      2801283.97     10165664.69
      2801455.82     10165378.28
#Sta/Elev= 30
  4355.3 1199.26  4405.3 1199.91  4566.5 1192.99  4722.6 1184.82  4822.6 1168.47
  4861.8 1167.05  4928.6 1163.55  4949.7 1160.96  4955.3 1157.82  4956.8 1156.82
    5029 1157.82  5069.2 1165.15  5105.3 1171.82  5147.8 1189.24  5183.3 1198.28
  5211.6    1201  5246.8 1198.94    5276 1199.75  5296.1 1201.75  5311.6 1198.43
    5333 1200.67  5348.6 1197.83  5354.4 1199.93  5369.9 1197.73  5385.5  1198.4
  5391.3 1200.66  5421.7 1202.44  5469.5 1209.61  5510.4 1211.04  5613.9 1209.55
#Mann= 10 ,-1 , 0
  4355.3     .12       0  4566.5     .05       0  4722.6     .12       0
  4861.8     .05       0  4955.3     .05       0    5029     .05       0
  5069.2     .12       0    5276     .05       0  5469.5     .12       0
  5510.4     .05       0
Bank Sta=4955.3,5029
XS Rating Curve= 0 ,0
Exp/Cntr=0.3,0.1

Type RM Length L Ch R = 1 ,3266    ,313,313,313
BEGIN DESCRIPTION:
CRABAPPLE CREEK 5.0
END DESCRIPTION:
XS GIS Cut Line= 3
      2800961.07     10166633.44      2801610.04     10166261.95
       2801805.7      10166103.1
#Sta/Elev= 30
  4522.3 1198.26  4613.8 1195.38  4769.2 1185.34  4812.4 1172.88  4861.8  1164.6
  4920.3 1162.38  4942.4 1158.71  4973.5 1158.78  4974.1 1157.14  4975.6 1156.14
  5047.8 1157.14  5069.2 1158.85  5096.9 1163.69  5126.8 1168.91  5156.3 1178.96
  5177.9 1182.37  5193.7 1187.32  5199.5 1186.25  5215.3 1190.68  5221.1  1189.1
  5236.9 1192.65  5279.4 1195.58  5302.3 1198.74  5308.7 1197.68  5323.1  1200.3
  5366.2 1197.35  5372.7 1195.69  5393.5 1197.07  5465.3 1211.77  5522.1 1214.07
#Mann= 5 ,-1 , 0
  4522.3     .05       0  4974.1     .05       0  5047.8     .05       0
  5096.9     .12       0  5279.4     .05       0
Bank Sta=4974.1,5047.8
XS Rating Curve= 0 ,0
Exp/Cntr=0.3,0.1

Type RM Length L Ch R = 1 ,2953    ,753,753,753
BEGIN DESCRIPTION:
CRABAPPLE CREEK 4.0
END DESCRIPTION:
XS GIS Cut Line= 3
      2801190.25     10166805.31      2801755.68     10166553.11
      2801986.71     10166357.73
#Sta/Elev= 30
  4571.7 1189.08  4707.8 1182.17  4732.1 1177.01  4736.5 1175.44  4774.7 1168.24
  4834.9 1161.94  4863.6 1161.29  4873.3 1160.24  4881.4 1157.76  4910.1 1158.04
  4917.1 1159.54    4962 1158.42  4966.1 1157.21  4967.6 1156.21  5038.3 1156.21
  5039.8 1157.21  5048.5 1163.08  5083.6 1168.29  5092.3 1171.54  5101.3 1176.75
  5124.6 1187.09    5130 1187.78  5136.1 1190.71  5153.3 1194.36  5218.8 1202.78
  5283.3 1205.91  5339.7 1208.33  5368.3 1207.92  5417.7 1209.41  5493.4 1208.53
#Mann= 5 ,-1 , 0
  4571.7     .12       0  4732.1     .05       0  4966.1     .05       0
  5039.8     .05       0  5283.3     .05       0
Bank Sta=4966.1,5039.8
XS Rating Curve= 0 ,0
Exp/Cntr=0.3,0.1

Type RM Length L Ch R = 1 ,2200    ,582,582,582
BEGIN DESCRIPTION:
CRABAPPLE CREEK 3.0
END DESCRIPTION:
XS GIS Cut Line= 3
      2801518.33     10167445.96      2802098.82     10167016.54
      2802405.69     10166703.11
#Sta/Elev= 30
  4401.2 1202.75  4444.7 1200.59  4551.1  1185.1  4654.1 1177.68  4680.6 1173.67
  4716.1 1164.34  4728.8 1164.28  4745.3 1163.48  4772.4 1156.96  4780.8 1158.02
    4787 1155.33  4816.3 1156.31  4822.5 1154.43  4830.9 1155.37  4837.1 1158.94
  4845.5 1155.64  4851.7 1160.01  4895.5 1159.93  4971.4  1151.2  4972.9  1150.2
  5045.2  1151.2  5066.8 1153.51    5099 1164.23  5116.9  1168.7  5121.9 1172.95
  5201.2 1182.17  5250.8 1193.17  5344.3 1196.63  5448.8  1196.8  5561.9 1193.37
#Mann= 7 ,-1 , 0
  4401.2     .05       0  4654.1     .12       0  4728.8     .05       0
  4971.4     .05       0  5045.2     .05       0    5099     .12       0
  5344.3     .05       0
Bank Sta=4971.4,5045.2
XS Rating Curve= 0 ,0
Exp/Cntr=0.3,0.1

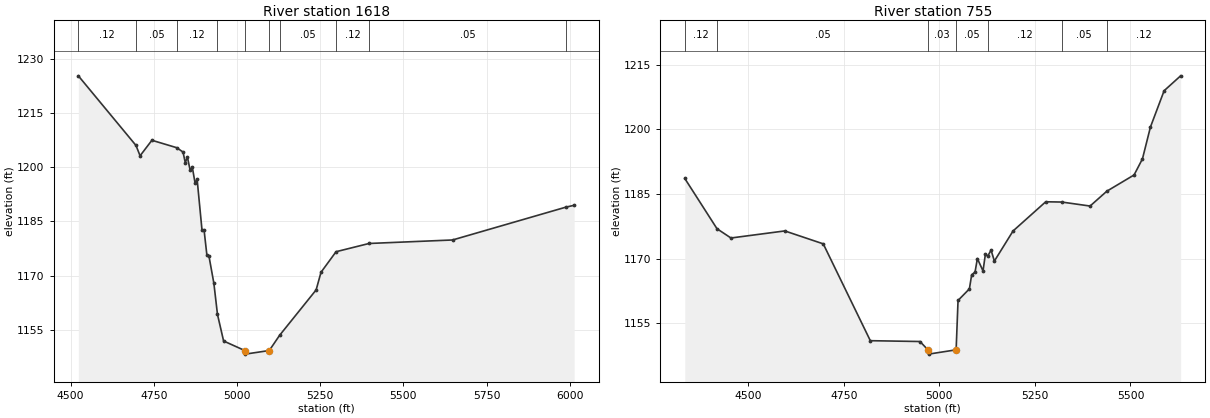
Type RM Length L Ch R = 1 ,1618    ,863,863,863
BEGIN DESCRIPTION:
CRABAPPLE CREEK 2.0
END DESCRIPTION:
XS GIS Cut Line= 3
      2802080.87     10167857.38      2802586.05     10167164.69
      2803200.63     10167013.65
#Sta/Elev= 30
    4523 1225.31  4696.3 1206.02  4708.6 1203.16  4744.1 1207.46  4818.8  1205.4
  4837.7 1204.19  4844.5 1201.21  4850.7 1202.87  4859.2 1199.09  4865.4  1200.1
  4873.9 1195.57    4880 1196.68  4894.7 1182.56  4900.9  1182.6  4909.4 1175.63
  4915.6 1175.36  4930.3 1167.88  4941.2 1159.21  4959.6 1151.86  5023.1 1149.22
  5024.6 1148.22  5096.9 1149.22    5128 1153.44  5237.7 1166.01  5252.4  1170.9
  5297.6 1176.59  5396.7 1178.87  5647.7 1179.84  5988.2 1188.93  6013.2 1189.45
#Mann= 10 ,-1 , 0
    4523     .12       0  4696.3     .05       0  4818.8     .12       0
  4941.2     .05       0  5023.1     .05       0  5096.9     .05       0
    5128     .05       0  5297.6     .12       0  5396.7     .05       0
  5988.2     .12       0
Bank Sta=5023.1,5096.9
XS Rating Curve= 0 ,0
Exp/Cntr=0.3,0.1

Type RM Length L Ch R = 1 ,755     ,0,0,0
BEGIN DESCRIPTION:
CRABAPPLE CREEK 1.0
END DESCRIPTION:
XS GIS Cut Line= 3
       2802555.7     10168053.11      2802929.41     10168009.61
      2803455.69      10167253.1
#Sta/Elev= 30
  4333.5  1188.6  4417.8 1176.93  4454.3 1174.78  4595.2 1176.42  4695.9 1173.42
  4819.1 1150.93  4949.1 1150.74  4969.9 1148.81  4971.4 1147.81  5043.7 1148.81
  5048.7 1160.28  5078.4 1162.96  5084.4 1166.24  5093.2 1166.86  5099.3 1170.01
  5114.1 1167.13  5120.2 1170.97  5126.5 1170.58  5135.1 1171.97  5143.8 1169.42
  5192.7 1176.41  5278.2 1183.19  5320.1 1183.13  5394.3  1182.2  5438.2 1185.65
  5509.5 1189.42  5531.4 1193.16  5552.3 1200.55  5588.1 1208.98  5631.3 1212.44
#Mann= 7 ,-1 , 0
  4333.5     .12       0  4417.8     .05       0  4969.9     .03       0
  5043.7     .05       0  5126.5     .12       0  5320.1     .05       0
  5438.2     .12       0
Bank Sta=4969.9,5043.7
XS Rating Curve= 0 ,0
Exp/Cntr=0.3,0.1

Chan Stop Cuts=-1
Use User Specified Reach Order=0
Composite Channel Slope=5