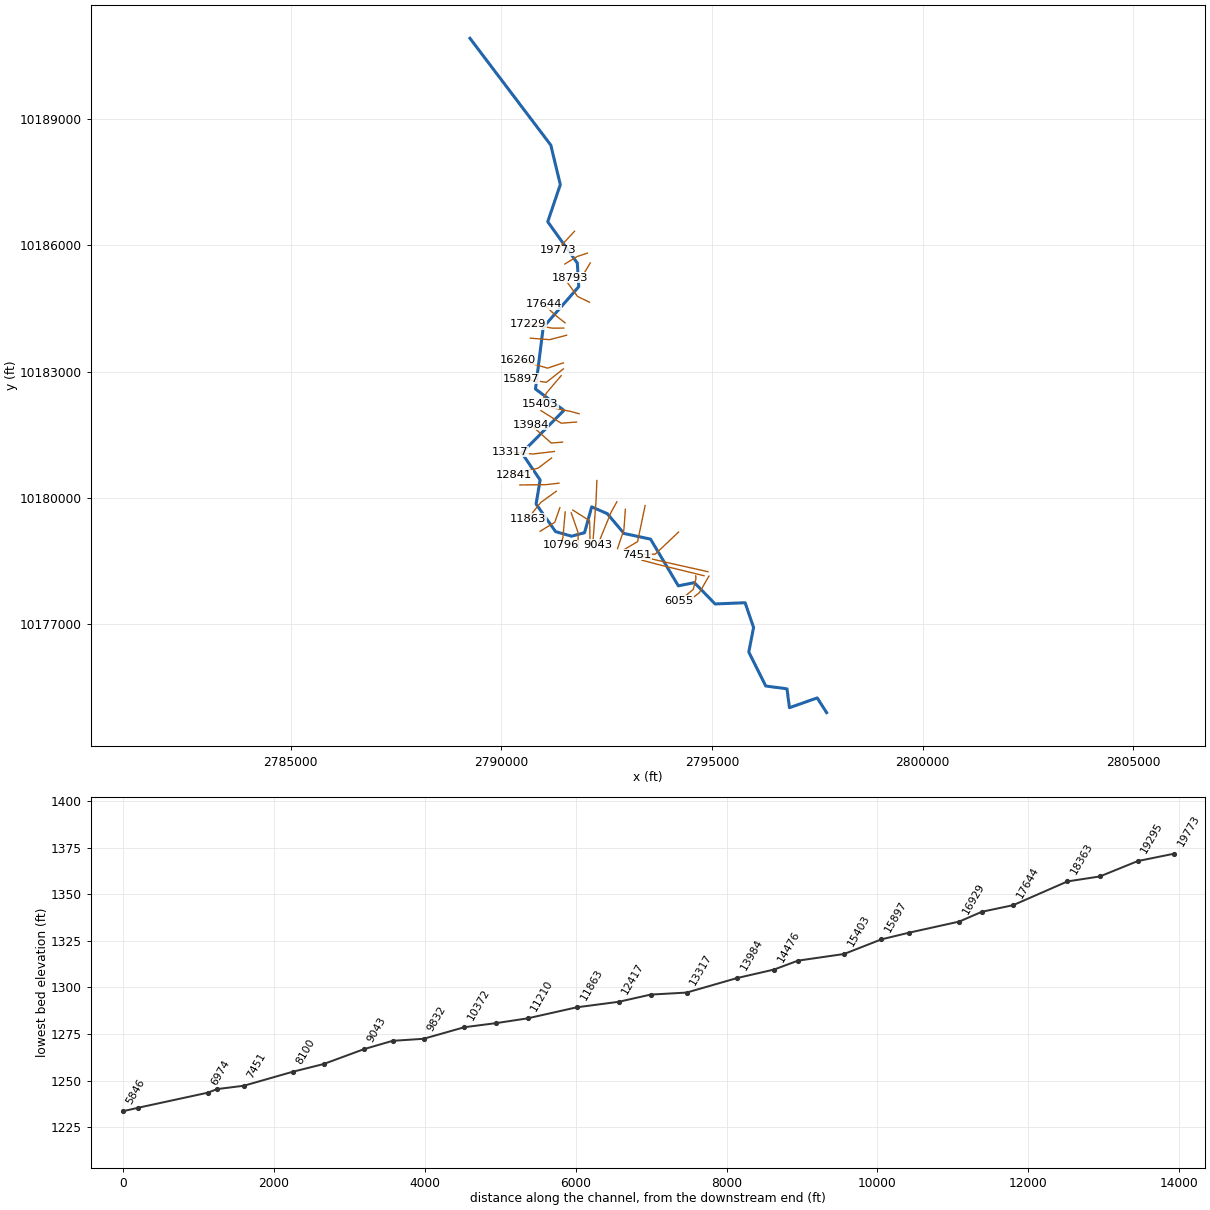
--- GOLDMINE CREEK.prj (project) ---

Proj Title=GOLDMINE CREEK Base Level Engineering
Current Plan=p01
Default Exp/Contr=0.3,0.1
English Units
Geom File=g01
Flow File=f01
Plan File=p01
BEGIN DESCRIPTION:
GOLDMINE CREEK
END DESCRIPTION:

--- GOLDMINE CREEK.p01 (plan) ---

Plan Title=Multiple Run
Short Identifier=Multiple
Geom File=g01
Flow File=f01
Subcritical Flow
K Sum by GR= 0
Std Step Tol= 0.01
Critical Tol= 0.01
Num of Std Step Trials= 20
Max Error Tol= 0.3
Flow Tol Ratio= 0.001
Split Flow NTrial= 30
Split Flow Tol= 0.02
Split Flow Ratio= 0.02
Log Output Level= 0
Friction Slope Method= 1
Unsteady Friction Slope Method= 2
Unsteady Bridges Friction Slope Method= 1
Parabolic Critical Depth
Global Vel Dist=  1 , 1 , 1
Global Log Level= 0
CheckData=True
Encroach Param= -1, 0, 0, 0
BEGIN DESCRIPTION:
Multiple Run
END DESCRIPTION:

--- GOLDMINE CREEK.f01 (steady flow) ---

Flow Title=Multiple
Number of Profiles=7
Profile Names=10-year,25-year,50-year,1pct_min,100-year,1pct_plu,500-year
River Rch & RM= GOLDMINE CREEK,Reach-1,19773
     417     670    1231     999    1699    2889    2419
River Rch & RM= GOLDMINE CREEK,Reach-1,17644
     887    1515    2508    1760    3521    7046    4987
River Rch & RM= GOLDMINE CREEK,Reach-1,4793
    1068    1852    2993    2042    4220    8724    5965
Boundary for River Rch & Prof#=GOLDMINE CREEK,Reach-1,1
Up Type=0
Dn Type=3
Dn Slope=0.005
Boundary for River Rch & Prof#=GOLDMINE CREEK,Reach-1,2
Up Type=0
Dn Type=3
Dn Slope=0.005
Boundary for River Rch & Prof#=GOLDMINE CREEK,Reach-1,3
Up Type=0
Dn Type=3
Dn Slope=0.005
Boundary for River Rch & Prof#=GOLDMINE CREEK,Reach-1,4
Up Type=0
Dn Type=3
Dn Slope=0.005
Boundary for River Rch & Prof#=GOLDMINE CREEK,Reach-1,5
Up Type=0
Dn Type=3
Dn Slope=0.005
Boundary for River Rch & Prof#=GOLDMINE CREEK,Reach-1,6
Up Type=0
Dn Type=3
Dn Slope=0.005
Boundary for River Rch & Prof#=GOLDMINE CREEK,Reach-1,7
Up Type=0
Dn Type=3
Dn Slope=0.005

--- GOLDMINE CREEK.g01 (geometry) ---

Geom Title=Existing Conditions

River Reach=GOLDMINE CREEK,Reach-1
Reach XY= 30
      2789255.00     10190910.00      2791173.25     10188376.00
      2791399.75     10187438.00      2791101.25     10186556.00
      2791803.50     10185576.00      2791837.25     10185016.00
      2790994.00     10184050.00      2790809.75     10182588.00
      2791483.75     10182080.00      2790486.00     10181069.00
      2790920.00     10180428.00      2790825.00     10179857.00
      2791287.75     10179202.00      2791665.00     10179094.00
      2791974.50     10179177.00      2792144.00     10179790.00
      2792515.75     10179628.00      2792911.00     10179159.00
      2793541.75     10179024.00      2794200.50     10177916.00
      2794581.25     10177992.00      2795073.75     10177486.00
      2795785.50     10177515.00      2795986.75     10176928.00
      2795873.00     10176346.00      2796274.75     10175539.00
      2796780.00     10175472.00      2796837.75     10175024.00
      2797497.25     10175256.00      2797720.50     10174907.00

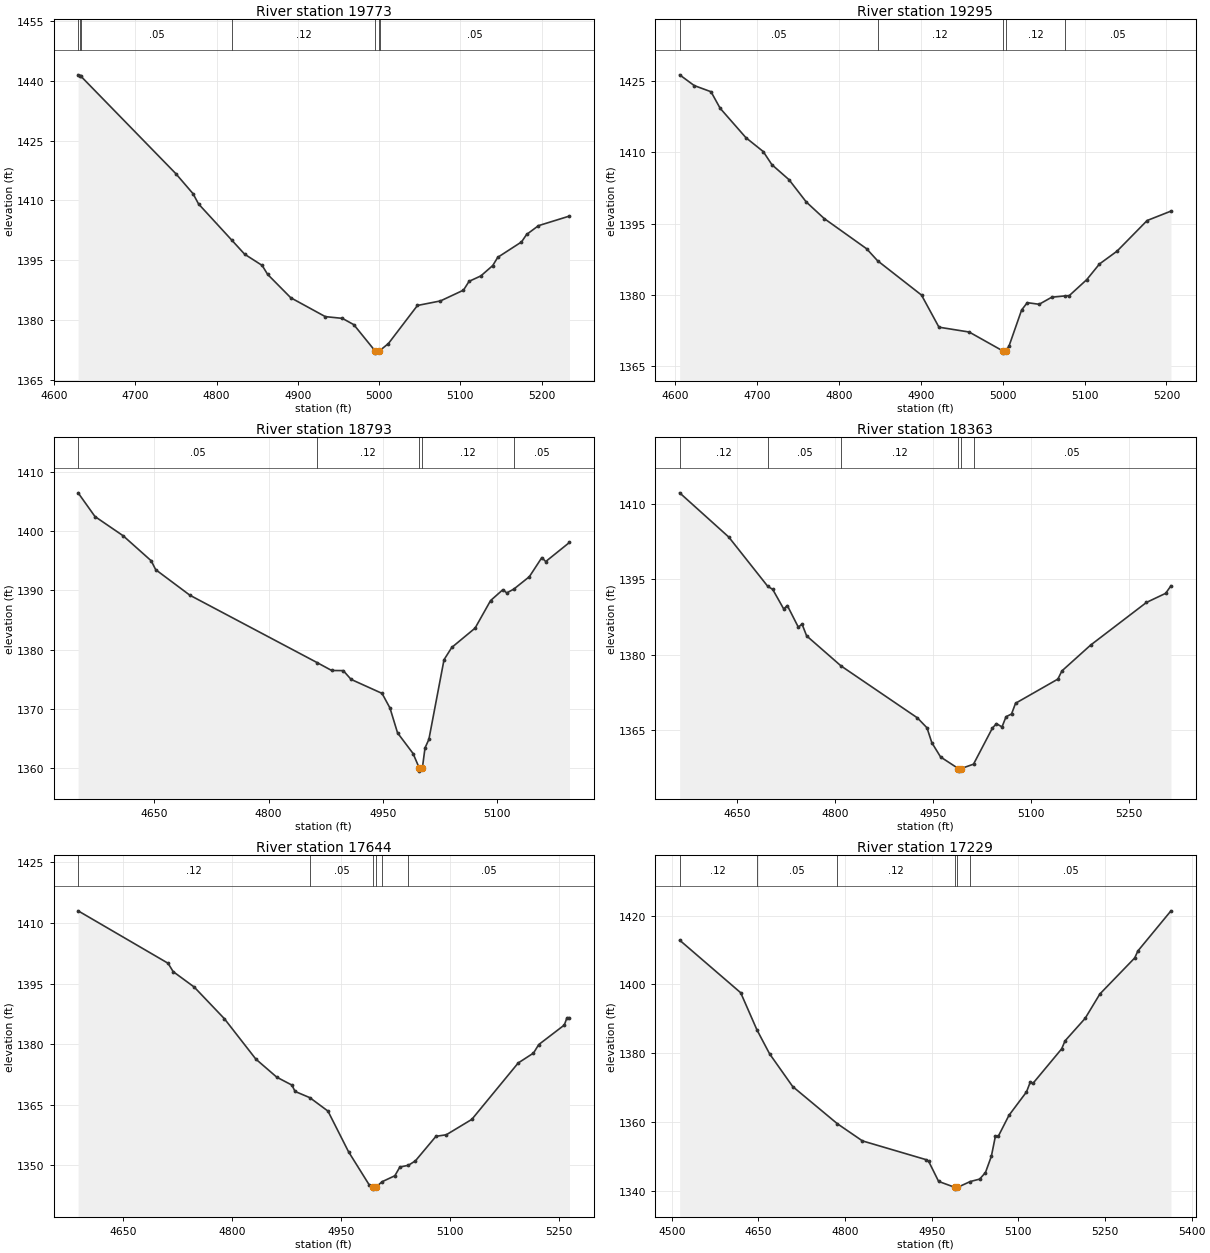
Type RM Length L Ch R = 1,19773,478,478,478
BEGIN DESCRIPTION:
GOLDMINE CREEK 41.0
END DESCRIPTION:
XS GIS Cut Line= 3
      2791737.45     10186331.10      2791409.51     10185977.93
      2791336.38     10185879.58
#Sta/Elev= 30
  4629.7 1441.55  4632.5 1441.36  4633.4 1441.14  4749.8 1416.76  4771.1 1411.70
  4777.9 1409.12  4819.1 1399.96  4834.6 1396.50  4856.1 1393.69  4862.9 1391.43
  4891.3 1385.57  4933.8 1380.83  4954.8 1380.39  4968.9 1378.81  4995.3 1372.16
  4995.5 1371.66  4999.3 1372.16  5000.7 1372.27  5011.5 1374.07  5047.2 1383.63
  5075.5 1384.77  5103.8 1387.47  5110.7 1389.69  5125.2 1391.05  5139.8 1393.65
  5146.0 1395.72  5175.2 1399.58  5181.5 1401.46  5196.1 1403.67  5234.2 1406.08
#Mann=7,-1,0
  4629.7    0.05       0  4632.5    0.12       0  4633.4    0.05       0
  4819.1    0.12       0  4995.3    0.07       0  4999.3    0.12       0
  5000.7    0.05       0
Bank Sta=4995.3,4999.3
Exp/Cntr=0.3,0.1

Type RM Length L Ch R = 1,19295,502,502,502
BEGIN DESCRIPTION:
GOLDMINE CREEK 40.0
END DESCRIPTION:
XS GIS Cut Line= 3
      2792042.63     10185811.44      2791803.02     10185733.25
      2791505.68     10185553.11
#Sta/Elev= 30
  4605.8 1426.31  4623.6 1424.05  4644.1 1422.75  4655.2 1419.28  4686.7 1413.08
  4707.8 1410.17  4718.4 1407.40  4739.3 1404.24  4760.4 1399.54  4782.2 1396.07
  4834.0 1389.71  4847.4 1387.18  4901.0 1379.96  4922.3 1373.20  4959.2 1372.18
  4999.9 1368.24  5000.1 1367.74  5003.9 1368.24  5007.7 1369.17  5023.2 1376.82
  5030.1 1378.36  5044.6 1378.02  5060.0 1379.51  5076.7 1379.79  5081.4 1379.85
  5102.7 1383.21  5118.2 1386.50  5139.6 1389.19  5176.4 1395.65  5205.5 1397.63
#Mann=5,-1,0
  4605.8    0.05       0  4847.4    0.12       0  4999.9    0.07       0
  5003.9    0.12       0  5076.7    0.05       0
Bank Sta=4999.9,5003.9
Exp/Cntr=0.3,0.1

Type RM Length L Ch R = 1,18793,430,430,430
BEGIN DESCRIPTION:
GOLDMINE CREEK 39.0
END DESCRIPTION:
XS GIS Cut Line= 3
      2792110.74     10185579.34      2791939.23     10185291.81
      2791633.98     10185231.26
#Sta/Elev= 30
  4549.6 1406.42  4571.8 1402.42  4608.8 1399.18  4645.7 1394.96  4651.6 1393.46
  4696.6 1389.15  4863.7 1377.80  4883.0 1376.46  4898.2 1376.44  4908.5 1374.96
  4949.2 1372.60  4959.6 1370.14  4969.6 1365.94  4990.0 1362.46  4998.2 1359.99
  4998.4 1359.49  5002.2 1359.99  5005.7 1363.40  5010.8 1364.85  5030.7 1378.28
  5040.9 1380.35  5071.5 1383.60  5091.9 1388.25  5108.1 1390.09  5113.2 1389.54
  5122.5 1390.19  5142.9 1392.28  5159.3 1395.50  5164.4 1394.83  5195.6 1398.05
#Mann=5,-1,0
  4549.6    0.05       0  4863.7    0.12       0  4998.2    0.07       0
  5002.2    0.12       0  5122.5    0.05       0
Bank Sta=4998.2,5002.2
Exp/Cntr=0.3,0.1

Type RM Length L Ch R = 1,18363,719,719,719
BEGIN DESCRIPTION:
GOLDMINE CREEK 38.0
END DESCRIPTION:
XS GIS Cut Line= 3
      2792090.55     10184646.07      2791808.06     10184784.79
      2791549.11     10185139.27
#Sta/Elev= 30
  4561.3 1412.24  4636.6 1403.44  4696.5 1393.61  4704.0 1393.02  4720.9 1389.12
  4726.5 1389.79  4743.4 1385.47  4749.0 1386.11  4756.1 1383.75  4808.9 1377.76
  4926.0 1367.42  4940.7 1365.44  4948.2 1362.46  4961.6 1359.63  4988.9 1357.31
  4989.2 1356.81  4992.9 1357.31  5012.1 1358.20  5041.1 1365.39  5047.3 1366.27
  5055.8 1365.61  5062.0 1367.65  5070.4 1368.19  5076.6 1370.33  5141.5 1375.14
  5147.7 1376.77  5191.7 1381.91  5277.4 1390.41  5306.8 1392.22  5315.0 1393.73
#Mann=6,-1,0
  4561.3    0.12       0  4696.5    0.05       0  4808.9    0.12       0
  4988.9    0.07       0  4992.9    0.12       0  5012.1    0.05       0
Bank Sta=4988.9,4992.9
Exp/Cntr=0.3,0.1

Type RM Length L Ch R = 1,17644,415,415,415
BEGIN DESCRIPTION:
GOLDMINE CREEK 37.0
END DESCRIPTION:
XS GIS Cut Line= 3
      2791512.92     10184156.70      2791275.82     10184343.35
      2791005.70     10184603.10
#Sta/Elev= 30
  4588.0 1413.01  4711.8 1400.03  4718.9 1397.95  4747.8 1394.14  4789.4 1386.29
  4832.7 1376.29  4861.6 1371.80  4882.4 1369.85  4886.7 1368.28  4907.1 1366.73
  4932.0 1363.41  4960.3 1353.35  4988.6 1345.19  4993.7 1344.58  4994.0 1344.08
  4997.9 1344.58  5006.7 1345.93  5024.1 1347.39  5031.0 1349.55  5042.8 1349.99
  5052.4 1351.08  5080.7 1357.16  5094.9 1357.54  5130.1 1361.36  5193.9 1375.32
  5215.0 1377.78  5222.2 1379.88  5257.4 1384.72  5261.1 1386.53  5264.5 1386.53
#Mann=6,-1,0
  4588.0    0.12       0  4907.1    0.05       0  4993.7    0.05       0
  4997.9    0.05       0  5006.7    0.12       0  5042.8    0.05       0
Bank Sta=4993.7,4997.9
Exp/Cntr=0.3,0.1

Type RM Length L Ch R = 1,17229,300,300,300
BEGIN DESCRIPTION:
GOLDMINE CREEK 36.0
END DESCRIPTION:
XS GIS Cut Line= 3
      2791481.40     10184032.93      2791215.14     10184030.92
      2790639.15     10184128.68
#Sta/Elev= 30
  4513.7 1412.86  4619.4 1397.58  4647.5 1386.80  4669.4 1379.84  4709.4 1370.33
  4786.7 1359.53  4830.1 1354.54  4939.5 1349.13  4944.6 1348.65  4962.0 1342.77
  4990.3 1341.03  4990.6 1340.53  4994.6 1341.03  5016.8 1342.74  5033.0 1343.44
  5043.1 1345.36  5053.3 1350.09  5060.2 1355.85  5065.2 1355.86  5083.7 1361.96
  5114.1 1368.77  5120.5 1371.57  5125.5 1371.30  5175.0 1381.29  5180.8 1383.60
  5215.6 1390.14  5241.1 1397.22  5301.4 1407.69  5306.9 1409.72  5364.2 1421.38
#Mann=6,-1,0
  4513.7    0.12       0  4647.5    0.05       0  4786.7    0.12       0
  4990.3    0.07       0  4994.6    0.12       0  5016.8    0.05       0
Bank Sta=4990.3,4994.6
Exp/Cntr=0.3,0.1

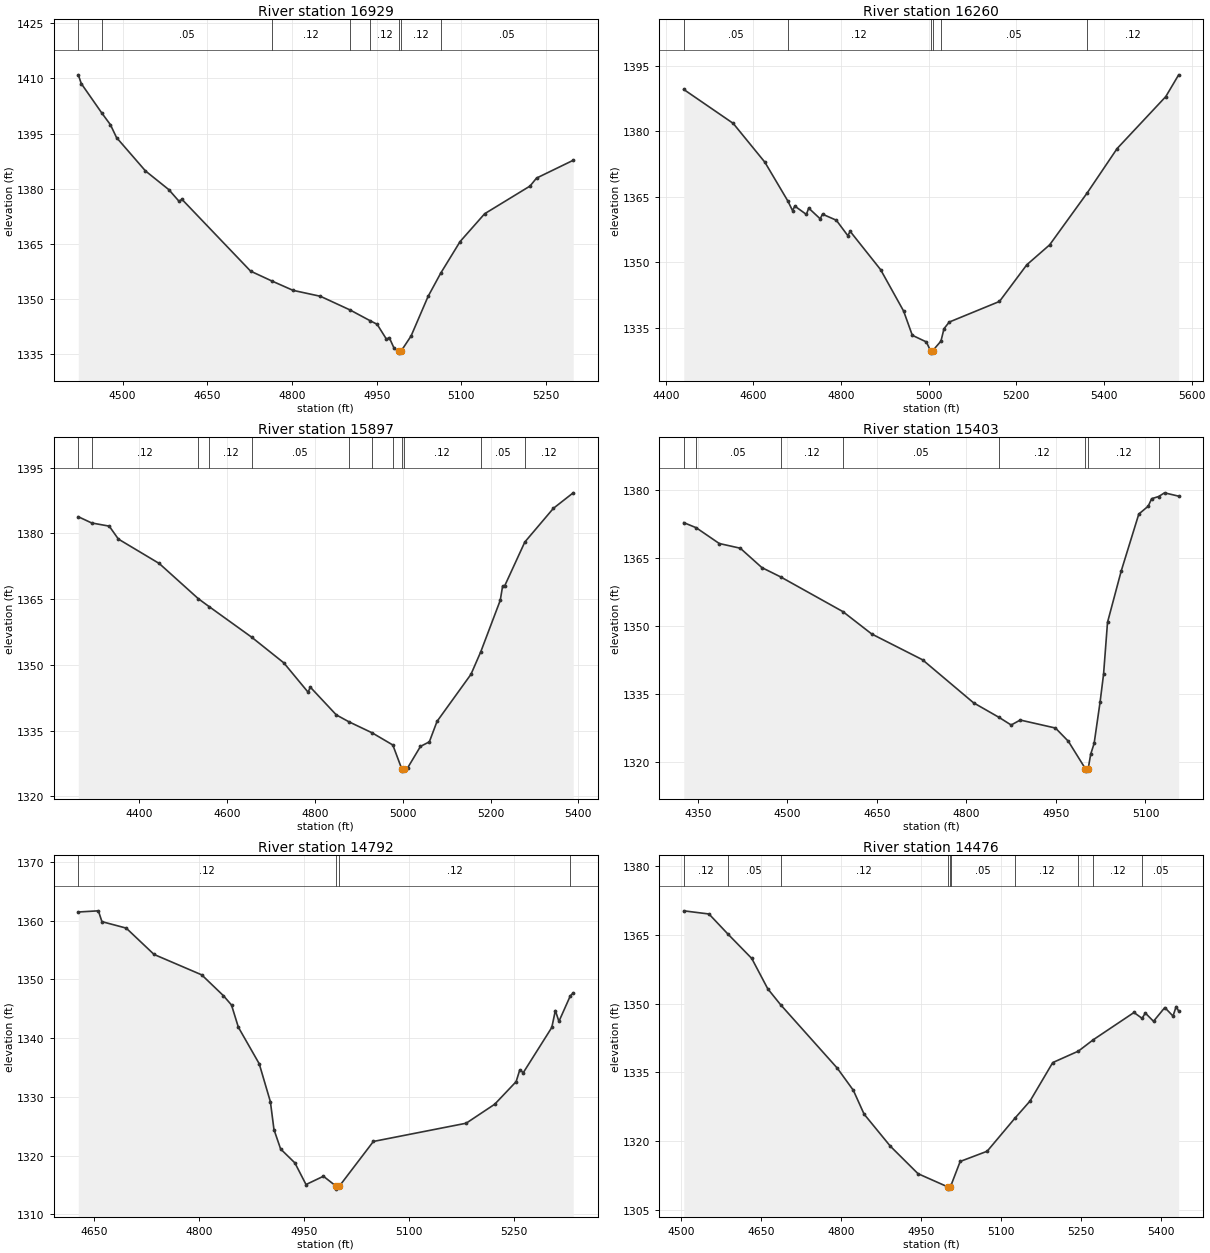
Type RM Length L Ch R = 1,16929,669,669,669
BEGIN DESCRIPTION:
GOLDMINE CREEK 35.0
END DESCRIPTION:
XS GIS Cut Line= 3
      2791550.77     10183864.08      2791147.17     10183758.14
      2790689.39     10183793.35
#Sta/Elev= 30
  4421.6 1410.98  4426.9 1408.60  4463.1 1400.62  4478.5 1397.41  4489.3 1393.92
  4540.6 1384.83  4581.9 1379.75  4600.0 1376.58  4605.2 1377.11  4726.7 1357.58
  4764.0 1354.92  4801.9 1352.35  4850.4 1350.73  4902.9 1347.01  4938.7 1344.06
  4950.7 1343.13  4967.3 1339.07  4972.3 1339.48  4980.8 1336.61  4988.7 1335.77
  4989.0 1335.27  4993.0 1335.77  5010.9 1339.93  5041.0 1350.69  5063.3 1357.00
  5097.7 1365.62  5141.2 1373.19  5221.5 1380.72  5233.1 1382.89  5298.0 1387.73
#Mann=8,-1,0
  4421.6    0.12       0  4463.1    0.05       0  4764.0    0.12       0
  4902.9    0.05       0  4938.7    0.12       0  4988.7    0.07       0
  4993.0    0.12       0  5063.3    0.05       0
Bank Sta=4988.7,4993
Exp/Cntr=0.3,0.1

Type RM Length L Ch R = 1,16260,363,363,363
BEGIN DESCRIPTION:
GOLDMINE CREEK 34.0
END DESCRIPTION:
XS GIS Cut Line= 3
      2791472.60     10183208.24      2791096.72     10183082.11
      2790392.95     10183286.43
#Sta/Elev= 30
  4441.1 1389.53  4553.9 1381.78  4626.3 1372.89  4678.5 1364.06  4689.3 1361.86
  4694.6 1362.87  4720.9 1360.97  4726.2 1362.42  4752.4 1359.97  4757.7 1361.03
  4789.2 1359.65  4815.5 1356.12  4820.8 1357.11  4890.2 1348.37  4942.8 1338.89
  4962.6 1333.36  4994.8 1331.83  5004.3 1329.78  5004.6 1329.28  5008.7 1329.78
  5028.0 1332.03  5034.9 1334.86  5046.9 1336.38  5161.5 1341.09  5223.9 1349.47
  5276.0 1354.02  5361.7 1365.89  5430.0 1376.03  5541.0 1387.90  5570.4 1392.87
#Mann=6,-1,0
  4441.1    0.05       0  4678.5    0.12       0  5004.3    0.07       0
  5008.7    0.12       0  5028.0    0.05       0  5361.7    0.12       0
Bank Sta=5004.3,5008.7
Exp/Cntr=0.3,0.1

Type RM Length L Ch R = 1,15897,494,494,494
BEGIN DESCRIPTION:
GOLDMINE CREEK 33.0
END DESCRIPTION:
XS GIS Cut Line= 3
      2791472.61     10183064.48      2791068.97     10182746.62
      2790461.01     10182829.87
#Sta/Elev= 30
  4260.8 1383.83  4291.2 1382.41  4331.3 1381.68  4352.1 1378.73  4445.2 1373.15
  4534.2 1365.11  4559.0 1363.29  4655.8 1356.31  4728.9 1350.46  4784.3 1343.75
  4789.3 1344.91  4848.5 1338.57  4877.1 1337.00  4930.5 1334.45  4977.3 1331.69
  4997.7 1326.22  4998.0 1325.72  5002.1 1326.22  5010.9 1326.44  5040.3 1331.37
  5060.5 1332.41  5078.0 1337.08  5155.3 1347.83  5177.8 1353.02  5222.0 1364.73
  5227.4 1367.97  5232.5 1368.12  5278.0 1378.05  5343.1 1385.75  5388.2 1389.29
#Mann=12,-1,0
  4260.8    0.05       0  4291.2    0.12       0  4534.2    0.05       0
  4559.0    0.12       0  4655.8    0.05       0  4877.1    0.12       0
  4930.5    0.05       0  4977.3    0.12       0  4997.7    0.07       0
  5002.1    0.12       0  5177.8    0.05       0  5278.0    0.12       0
Bank Sta=4997.7,5002.1
Exp/Cntr=0.3,0.1

Type RM Length L Ch R = 1,15403,611,611,611
BEGIN DESCRIPTION:
GOLDMINE CREEK 32.0
END DESCRIPTION:
XS GIS Cut Line= 3
      2791419.62     10182903.03      2791076.54     10182499.41
      2790927.74     10182239.64
#Sta/Elev= 30
  4326.5 1372.84  4347.2 1371.72  4386.0 1368.22  4421.2 1367.18  4457.4 1362.89
  4488.6 1360.85  4593.1 1353.16  4641.4 1348.21  4726.5 1342.51  4812.0 1332.99
  4854.8 1329.76  4875.0 1328.08  4890.2 1329.18  4949.2 1327.41  4970.8 1324.48
  4999.5 1318.38  4999.8 1317.88  5004.0 1318.38  5008.2 1321.61  5014.0 1324.02
  5024.0 1333.20  5029.8 1339.33  5036.4 1350.78  5059.4 1362.16  5088.8 1374.73
  5104.6 1376.48  5110.3 1378.13  5122.0 1378.61  5131.9 1379.43  5155.6 1378.69
#Mann=8,-1,0
  4326.5    0.12       0  4347.2    0.05       0  4488.6    0.12       0
  4593.1    0.05       0  4854.8    0.12       0  4999.5    0.07       0
  5004.0    0.12       0  5122.0    0.05       0
Bank Sta=4999.5,5004
Exp/Cntr=0.3,0.1

Type RM Length L Ch R = 1,14792,316,316,316
BEGIN DESCRIPTION:
GOLDMINE CREEK 31.0
END DESCRIPTION:
XS GIS Cut Line= 3
      2791845.93     10181999.95      2791638.37     10182056.27
      2791155.66     10182153.12
#Sta/Elev= 30
  4627.1 1361.45  4655.8 1361.65  4660.9 1359.81  4695.6 1358.71  4735.4 1354.23
  4803.5 1350.76  4834.6 1347.21  4846.1 1345.63  4855.9 1341.85  4885.7 1335.64
  4901.7 1329.17  4906.8 1324.44  4916.3 1321.14  4936.7 1318.77  4952.6 1315.09
  4977.5 1316.50  4995.6 1314.81  4995.9 1314.31  5000.2 1314.81  5048.9 1322.42
  5181.5 1325.52  5222.3 1328.75  5252.9 1332.59  5258.1 1334.57  5263.2 1334.13
  5303.9 1341.81  5309.0 1344.69  5314.1 1342.84  5330.3 1347.17  5334.5 1347.69
#Mann=4,-1,0
  4627.1    0.12       0  4995.6    0.07       0  5000.2    0.12       0
  5330.3    0.05       0
Bank Sta=4995.6,5000.2
Exp/Cntr=0.3,0.1

Type RM Length L Ch R = 1,14476,492,492,492
BEGIN DESCRIPTION:
GOLDMINE CREEK 30.0
END DESCRIPTION:
XS GIS Cut Line= 3
      2791782.87     10181803.21      2791419.60     10181775.46
      2790940.51     10182073.00
#Sta/Elev= 30
  4505.6 1370.28  4552.9 1369.59  4588.4 1365.22  4633.2 1359.88  4663.2 1353.26
  4687.1 1349.81  4793.6 1335.94  4823.7 1331.11  4843.8 1325.92  4893.1 1318.91
  4945.0 1312.91  5000.6 1310.04  5000.9 1309.54  5005.2 1310.04  5007.0 1310.40
  5024.1 1315.58  5074.7 1317.81  5126.4 1324.97  5155.2 1328.78  5197.7 1337.16
  5245.8 1339.66  5273.7 1342.14  5350.1 1348.09  5365.3 1346.81  5371.3 1347.98
  5386.7 1346.17  5407.9 1349.17  5423.3 1347.31  5429.2 1349.39  5433.9 1348.40
#Mann=10,-1,0
  4505.6    0.12       0  4588.4    0.05       0  4687.1    0.12       0
  5000.6    0.07       0  5005.2    0.12       0  5007.0    0.05       0
  5126.4    0.12       0  5245.8    0.05       0  5273.7    0.12       0
  5365.3    0.05       0
Bank Sta=5000.6,5005.2
Exp/Cntr=0.3,0.1

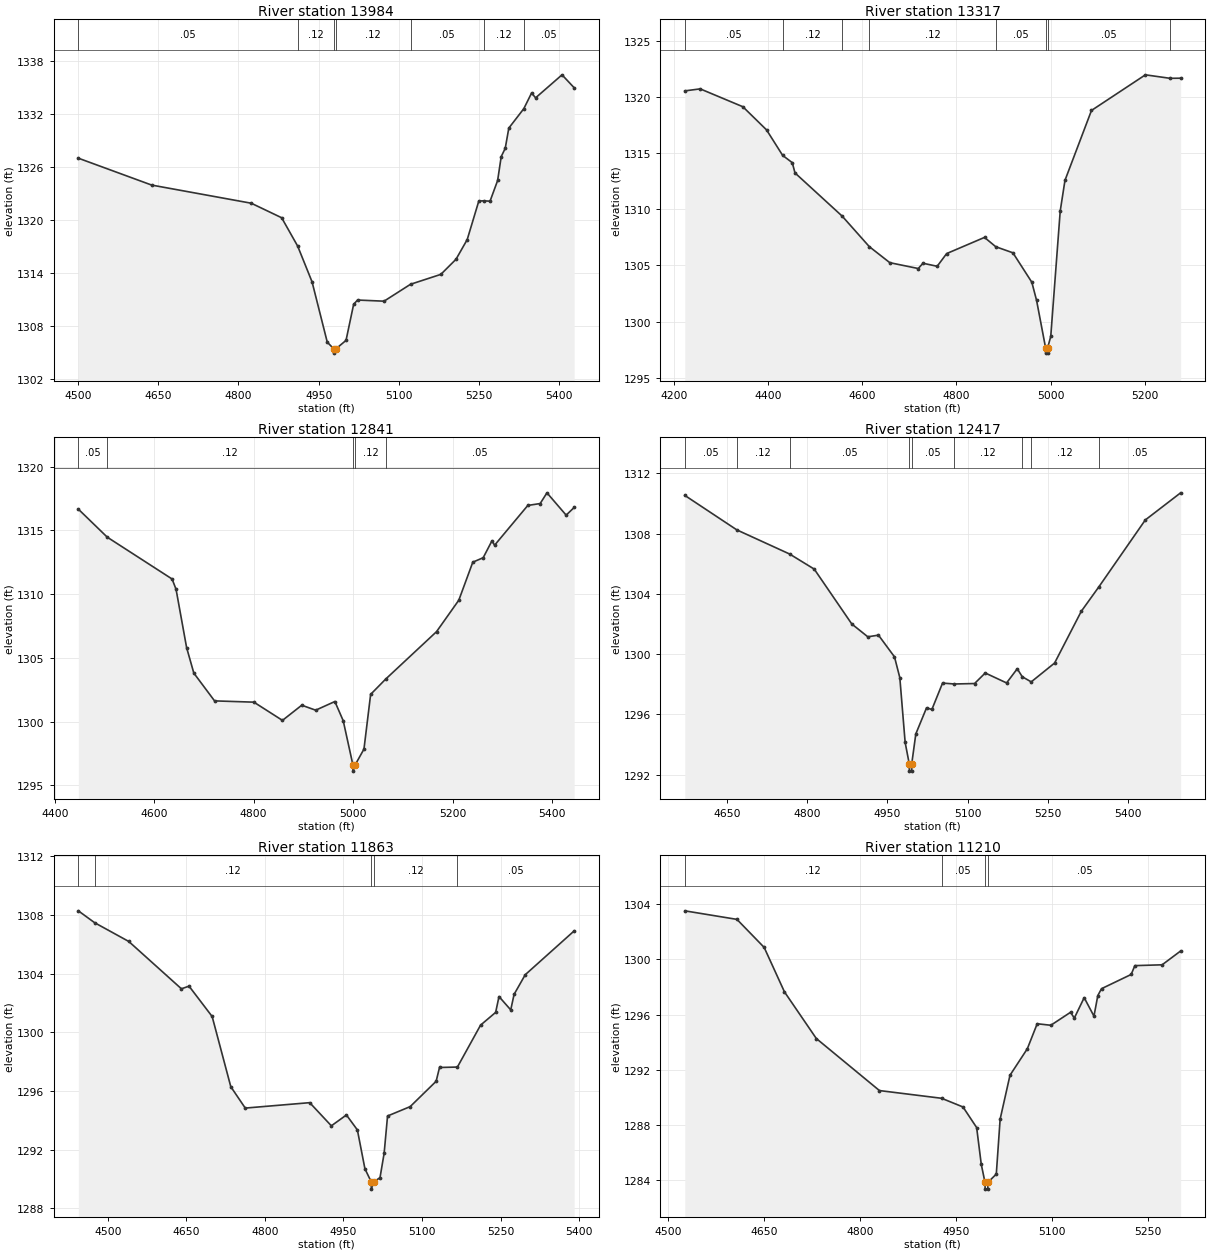
Type RM Length L Ch R = 1,13984,667,667,667
BEGIN DESCRIPTION:
GOLDMINE CREEK 29.0
END DESCRIPTION:
XS GIS Cut Line= 3
      2791452.42     10181326.46      2791185.76     10181304.08
      2790693.10     10181742.68
#Sta/Elev= 30
  4500.6 1326.99  4637.8 1323.95  4824.0 1321.90  4880.8 1320.26  4910.8 1317.05
  4937.7 1313.01  4966.1 1306.20  4978.0 1305.46  4978.3 1304.96  4982.6 1305.46
  5001.2 1306.40  5015.4 1310.47  5022.7 1310.96  5072.3 1310.83  5121.8 1312.74
  5178.5 1313.86  5206.9 1315.57  5227.8 1317.79  5249.5 1322.15  5259.3 1322.17
  5270.5 1322.13  5284.7 1324.47  5291.4 1327.17  5298.9 1328.10  5305.6 1330.39
  5333.7 1332.59  5348.2 1334.36  5355.7 1333.81  5405.1 1336.41  5427.8 1334.95
#Mann=7,-1,0
  4500.6    0.05       0  4910.8    0.12       0  4978.0    0.07       0
  4982.6    0.12       0  5121.8    0.05       0  5259.3    0.12       0
  5333.7    0.05       0
Bank Sta=4978,4982.6
Exp/Cntr=0.3,0.1

Type RM Length L Ch R = 1,13317,476,476,476
BEGIN DESCRIPTION:
GOLDMINE CREEK 28.0
END DESCRIPTION:
XS GIS Cut Line= 3
      2791258.12     10181104.47      2790738.89     10181043.94
      2790211.28     10181096.91
#Sta/Elev= 30
  4223.2 1320.53  4255.9 1320.71  4346.5 1319.12  4396.8 1317.06  4431.0 1314.79
  4451.5 1314.14  4457.2 1313.23  4557.5 1309.38  4615.0 1306.67  4658.6 1305.24
  4719.0 1304.72  4729.0 1305.19  4759.2 1304.92  4779.3 1306.05  4859.7 1307.49
  4883.6 1306.66  4920.0 1306.12  4960.2 1303.50  4970.3 1301.88  4989.3 1297.69
  4989.6 1297.19  4993.6 1297.19  4994.0 1297.69  5000.4 1298.68  5020.5 1309.84
  5030.6 1312.57  5086.9 1318.79  5201.4 1321.96  5253.7 1321.65  5276.2 1321.66
#Mann=8,-1,0
  4223.2    0.05       0  4431.0    0.12       0  4557.5    0.05       0
  4615.0    0.12       0  4883.6    0.05       0  4989.3    0.05       0
  4994.0    0.05       0  5253.7    0.12       0
Bank Sta=4989.3,4994
Exp/Cntr=0.3,0.1

Type RM Length L Ch R = 1,12841,424,424,424
BEGIN DESCRIPTION:
GOLDMINE CREEK 27.0
END DESCRIPTION:
XS GIS Cut Line= 3
      2791192.57     10180950.60      2790874.74     10180710.97
      2790300.18     10180542.13
#Sta/Elev= 30
  4447.5 1316.66  4505.7 1314.46  4636.0 1311.18  4644.0 1310.37  4665.2 1305.80
  4679.7 1303.80  4721.4 1301.62  4800.5 1301.52  4857.9 1300.09  4896.7 1301.28
  4924.7 1300.89  4963.3 1301.57  4980.1 1300.06  4999.5 1296.61  4999.8 1296.11
  5004.2 1296.61  5021.8 1297.84  5035.2 1302.13  5065.2 1303.32  5167.7 1307.05
  5212.5 1309.52  5240.6 1312.50  5261.5 1312.85  5279.2 1314.18  5284.4 1313.83
  5351.2 1316.95  5376.1 1317.10  5389.7 1317.94  5428.3 1316.19  5444.4 1316.79
#Mann=5,-1,0
  4447.5    0.05       0  4505.7    0.12       0  4999.5    0.07       0
  5004.2    0.12       0  5065.2    0.05       0
Bank Sta=4999.5,5004.2
Exp/Cntr=0.3,0.1

Type RM Length L Ch R = 1,12417,554,554,554
BEGIN DESCRIPTION:
GOLDMINE CREEK 26.0
END DESCRIPTION:
XS GIS Cut Line= 3
      2791366.67     10180352.78      2791063.93     10180317.46
      2790439.47     10180309.91
#Sta/Elev= 30
  4570.1 1310.53  4667.7 1308.24  4766.6 1306.64  4812.7 1305.64  4883.1 1302.00
  4913.1 1301.15  4933.1 1301.26  4963.1 1299.82  4973.1 1298.44  4983.1 1294.14
  4990.7 1292.74  4991.1 1292.24  4995.2 1292.24  4995.5 1292.74  5003.1 1294.71
  5023.2 1296.44  5033.2 1296.33  5053.2 1298.08  5075.3 1298.02  5113.2 1298.05
  5133.2 1298.75  5173.2 1298.09  5193.2 1299.03  5202.6 1298.50  5219.4 1298.16
  5263.2 1299.41  5313.2 1302.84  5346.5 1304.48  5433.2 1308.90  5499.4 1310.70
#Mann=9,-1,0
  4570.1    0.05       0  4667.7    0.12       0  4766.6    0.05       0
  4990.7    0.05       0  4995.5    0.05       0  5075.3    0.12       0
  5202.6    0.05       0  5219.4    0.12       0  5346.5    0.05       0
Bank Sta=4990.7,4995.5
Exp/Cntr=0.3,0.1

Type RM Length L Ch R = 1,11863,653,653,653
BEGIN DESCRIPTION:
GOLDMINE CREEK 25.0
END DESCRIPTION:
XS GIS Cut Line= 3
      2791303.55     10180161.06      2790935.28     10179893.68
      2790627.56     10179510.29
#Sta/Elev= 30
  4443.8 1308.29  4474.9 1307.48  4540.1 1306.20  4640.6 1302.97  4655.2 1303.15
  4699.3 1301.08  4734.9 1296.29  4762.5 1294.83  4885.6 1295.20  4926.9 1293.62
  4955.7 1294.36  4976.6 1293.34  4991.0 1290.69  5003.0 1289.80  5003.3 1289.30
  5007.8 1289.80  5019.8 1290.08  5027.7 1291.75  5034.2 1294.29  5077.4 1294.93
  5127.0 1296.66  5133.4 1297.60  5167.6 1297.63  5211.8 1300.49  5240.6 1301.36
  5247.0 1302.44  5269.4 1301.53  5275.8 1302.59  5297.1 1303.93  5390.5 1306.92
#Mann=5,-1,0
  4443.8    0.05       0  4474.9    0.12       0  5003.0    0.07       0
  5007.8    0.12       0  5167.6    0.05       0
Bank Sta=5003,5007.8
Exp/Cntr=0.3,0.1

Type RM Length L Ch R = 1,11210,414,414,414
BEGIN DESCRIPTION:
GOLDMINE CREEK 24.0
END DESCRIPTION:
XS GIS Cut Line= 3
      2791389.34     10179770.10      2791268.25     10179424.50
      2790920.43     10179210.26
#Sta/Elev= 30
  4526.0 1303.52  4607.5 1302.90  4650.0 1300.87  4681.7 1297.65  4731.5 1294.27
  4830.1 1290.50  4927.3 1289.94  4960.7 1289.31  4982.0 1287.82  4989.2 1285.16
  4995.0 1283.86  4995.3 1283.36  4999.4 1283.36  4999.8 1283.86  5012.7 1284.45
  5018.7 1288.43  5034.1 1291.61  5061.2 1293.53  5076.6 1295.34  5097.9 1295.23
  5128.7 1296.17  5134.6 1295.75  5150.0 1297.23  5165.3 1295.89  5171.3 1297.38
  5177.1 1297.88  5223.4 1298.91  5229.2 1299.55  5271.8 1299.61  5300.7 1300.61
#Mann=4,-1,0
  4526.0    0.12       0  4927.3    0.05       0  4995.0    0.05       0
  4999.8    0.05       0
Bank Sta=4995,4999.8
Exp/Cntr=0.3,0.1

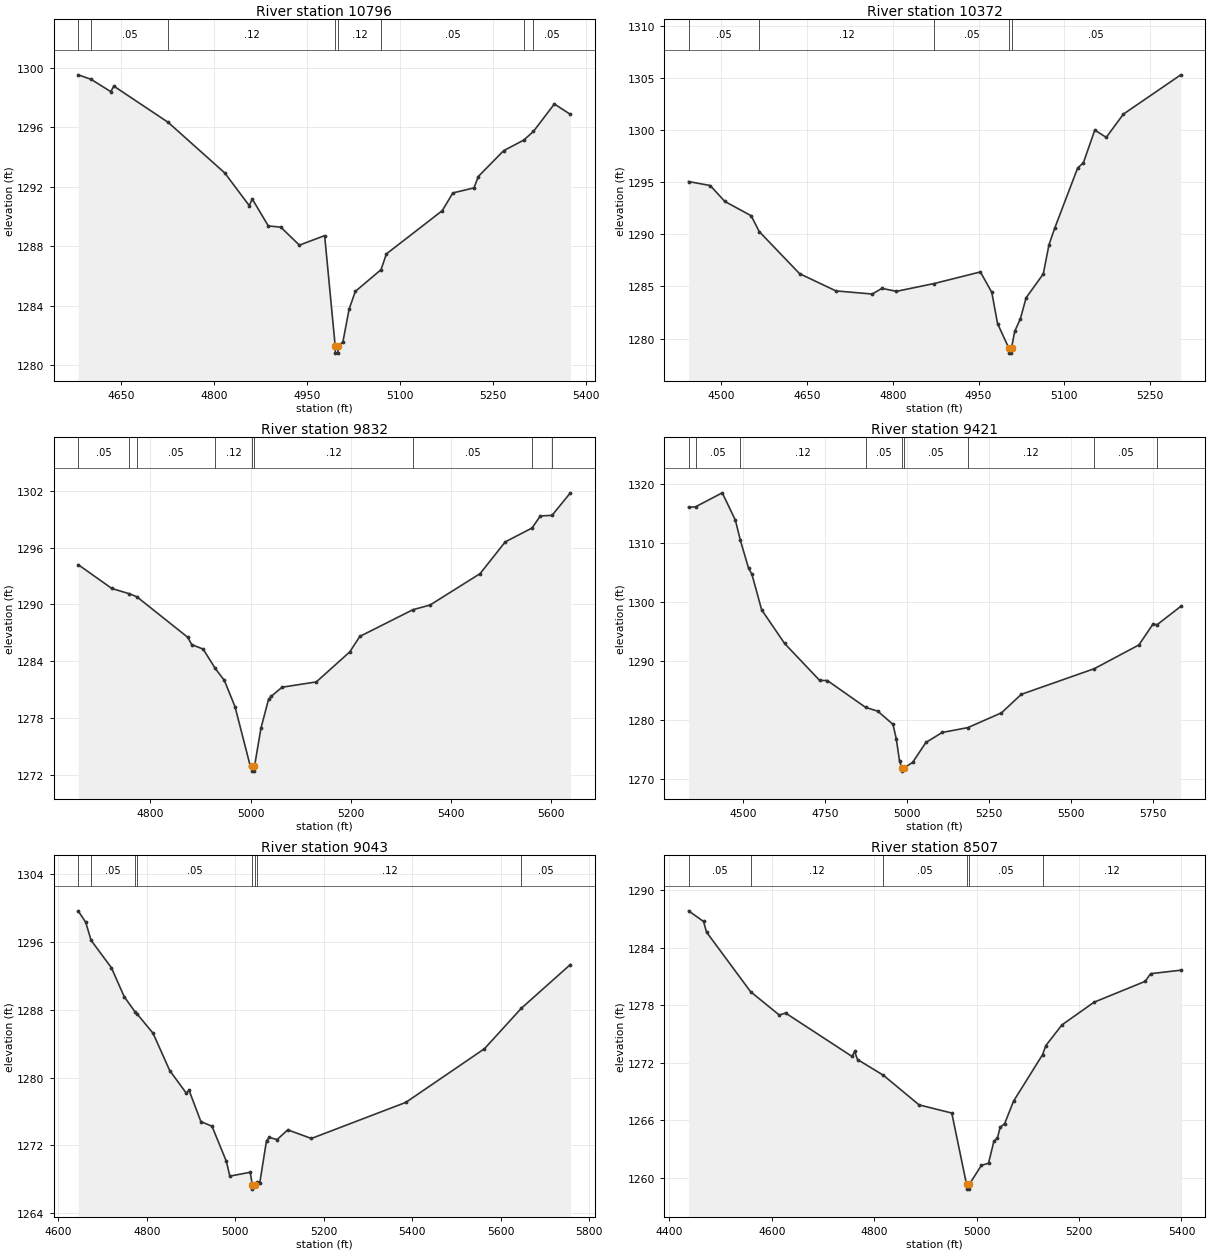
Type RM Length L Ch R = 1,10796,424,424,424
BEGIN DESCRIPTION:
GOLDMINE CREEK 23.0
END DESCRIPTION:
XS GIS Cut Line= 3
      2791515.46     10179669.22      2791462.48     10179071.35
      2791414.55     10178882.14
#Sta/Elev= 30
  4580.1 1299.53  4600.9 1299.23  4632.8 1298.40  4637.8 1298.77  4725.4 1296.34
  4817.1 1292.93  4856.5 1290.74  4861.5 1291.18  4887.4 1289.37  4907.5 1289.29
  4937.6 1288.08  4978.4 1288.72  4995.4 1281.32  4995.8 1280.82  4999.9 1280.82
  5000.2 1281.32  5007.9 1281.57  5017.9 1283.77  5028.0 1284.97  5069.5 1286.43
  5078.2 1287.49  5168.5 1290.40  5185.6 1291.59  5219.8 1291.93  5226.6 1292.69
  5267.6 1294.43  5300.1 1295.14  5315.7 1295.72  5349.6 1297.57  5375.5 1296.87
#Mann=8,-1,0
  4580.1    0.12       0  4600.9    0.05       0  4725.4    0.12       0
  4995.4    0.07       0  5000.2    0.12       0  5069.5    0.05       0
  5300.1    0.12       0  5315.7    0.05       0
Bank Sta=4995.4,5000.2
Exp/Cntr=0.3,0.1

Type RM Length L Ch R = 1,10372,540,540,540
BEGIN DESCRIPTION:
GOLDMINE CREEK 22.0
END DESCRIPTION:
XS GIS Cut Line= 3
      2791659.23     10179646.50      2791818.15     10179189.91
      2791830.72     10178812.78
#Sta/Elev= 30
  4442.9 1295.06  4480.7 1294.68  4506.4 1293.15  4552.4 1291.78  4566.5 1290.26
  4637.1 1286.22  4700.6 1284.57  4764.1 1284.27  4781.0 1284.81  4806.5 1284.53
  4872.7 1285.28  4953.2 1286.39  4973.2 1284.43  4983.2 1281.44  5002.8 1279.10
  5003.2 1278.60  5007.3 1278.60  5007.7 1279.10  5013.2 1280.68  5023.2 1281.91
  5033.2 1283.91  5063.2 1286.20  5073.2 1289.00  5083.2 1290.59  5123.3 1296.36
  5133.3 1296.86  5153.3 1300.00  5173.3 1299.30  5203.3 1301.53  5303.7 1305.30
#Mann=5,-1,0
  4442.9    0.05       0  4566.5    0.12       0  4872.7    0.05       0
  5002.8    0.05       0  5007.7    0.05       0
Bank Sta=5002.8,5007.7
Exp/Cntr=0.3,0.1

Type RM Length L Ch R = 1,9832,411,411,411
BEGIN DESCRIPTION:
GOLDMINE CREEK 21.0
END DESCRIPTION:
XS GIS Cut Line= 3
      2791694.53     10179714.60      2792095.63     10179459.81
      2792105.68     10178953.09
#Sta/Elev= 30
  4656.1 1294.20  4723.4 1291.68  4758.0 1291.13  4773.1 1290.81  4875.0 1286.52
  4882.6 1285.76  4905.5 1285.28  4929.6 1283.24  4947.8 1281.97  4969.0 1279.21
  4999.5 1272.93  5003.0 1272.90  5003.3 1272.40  5007.5 1272.40  5007.9 1272.90
  5020.7 1276.91  5035.9 1279.98  5041.8 1280.32  5063.0 1281.26  5131.3 1281.82
  5198.0 1284.99  5218.0 1286.62  5323.8 1289.44  5358.0 1289.93  5458.0 1293.25
  5508.1 1296.60  5561.7 1298.07  5578.1 1299.34  5601.5 1299.40  5638.1 1301.78
#Mann=9,-1,0
  4656.1    0.05       0  4758.0    0.12       0  4773.1    0.05       0
  4929.6    0.12       0  5003.0    0.07       0  5007.9    0.12       0
  5323.8    0.05       0  5561.7    0.12       0  5601.5    0.05       0
Bank Sta=5003,5007.9
Exp/Cntr=0.3,0.1

Type RM Length L Ch R = 1,9421,378,378,378
BEGIN DESCRIPTION:
GOLDMINE CREEK 20.0
END DESCRIPTION:
XS GIS Cut Line= 3
      2792267.15     10180415.81      2792246.98     10179923.95
      2792171.32     10178917.77
#Sta/Elev= 30
  4334.0 1316.02  4355.2 1316.10  4436.8 1318.47  4476.8 1313.83  4491.9 1310.44
  4516.9 1305.70  4526.9 1304.72  4556.9 1298.64  4626.9 1292.94  4733.9 1286.67
  4757.1 1286.66  4873.9 1282.11  4911.3 1281.46  4957.5 1279.22  4967.5 1276.78
  4977.5 1272.98  4984.9 1271.80  4985.3 1271.30  4990.2 1271.80  5017.7 1272.80
  5057.8 1276.16  5107.9 1277.86  5185.5 1278.67  5288.4 1281.18  5348.6 1284.31
  5571.8 1288.67  5707.5 1292.69  5749.7 1296.16  5763.8 1296.15  5835.3 1299.23
#Mann=9,-1,0
  4334.0    0.12       0  4355.2    0.05       0  4491.9    0.12       0
  4873.9    0.05       0  4984.9    0.05       0  4990.2    0.05       0
  5185.5    0.12       0  5571.8    0.05       0  5763.8    0.12       0
Bank Sta=4984.9,4990.2
Exp/Cntr=0.3,0.1

Type RM Length L Ch R = 1,9043,536,536,536
BEGIN DESCRIPTION:
GOLDMINE CREEK 19.0
END DESCRIPTION:
XS GIS Cut Line= 3
      2792741.37     10179908.79      2792605.67     10179664.50
      2792290.27     10178893.25
#Sta/Elev= 30
  4644.9 1299.66  4662.0 1298.31  4674.2 1296.18  4720.0 1292.96  4749.0 1289.54
  4773.8 1287.73  4777.6 1287.54  4814.2 1285.23  4851.9 1280.83  4889.7 1278.14
  4895.4 1278.53  4922.3 1274.82  4947.5 1274.26  4979.9 1270.13  4987.8 1268.38
  5033.9 1268.84  5038.5 1267.35  5039.0 1266.85  5043.9 1267.35  5050.2 1267.70
  5055.5 1267.61  5070.7 1272.57  5077.1 1272.94  5094.7 1272.69  5118.7 1273.84
  5172.1 1272.82  5385.8 1277.08  5563.3 1283.40  5646.9 1288.18  5757.6 1293.33
#Mann=8,-1,0
  4644.9    0.12       0  4674.2    0.05       0  4773.8    0.12       0
  4777.6    0.05       0  5038.5    0.05       0  5043.9    0.05       0
  5050.2    0.12       0  5646.9    0.05       0
Bank Sta=5038.5,5043.9
Exp/Cntr=0.3,0.1

Type RM Length L Ch R = 1,8507,407,407,407
BEGIN DESCRIPTION:
GOLDMINE CREEK 18.0
END DESCRIPTION:
XS GIS Cut Line= 3
      2792943.18     10179732.24      2792909.59     10179250.36
      2792756.81     10178797.28
#Sta/Elev= 30
  4437.5 1287.85  4466.7 1286.74  4472.6 1285.63  4558.6 1279.42  4614.6 1276.99
  4627.1 1277.19  4756.7 1272.67  4761.7 1273.19  4767.4 1272.35  4817.9 1270.71
  4887.7 1267.62  4951.5 1266.77  4980.3 1259.34  4980.7 1258.84  4985.3 1258.84
  4985.7 1259.34  5009.2 1261.31  5023.2 1261.54  5033.7 1263.83  5040.7 1264.18
  5045.9 1265.27  5054.8 1265.68  5072.1 1268.01  5128.8 1272.86  5135.1 1273.80
  5166.6 1275.96  5229.5 1278.33  5329.2 1280.50  5339.8 1281.30  5398.7 1281.66
#Mann=6,-1,0
  4437.5    0.05       0  4558.6    0.12       0  4817.9    0.05       0
  4980.3    0.05       0  4985.7    0.05       0  5128.8    0.12       0
Bank Sta=4980.3,4985.7
Exp/Cntr=0.3,0.1

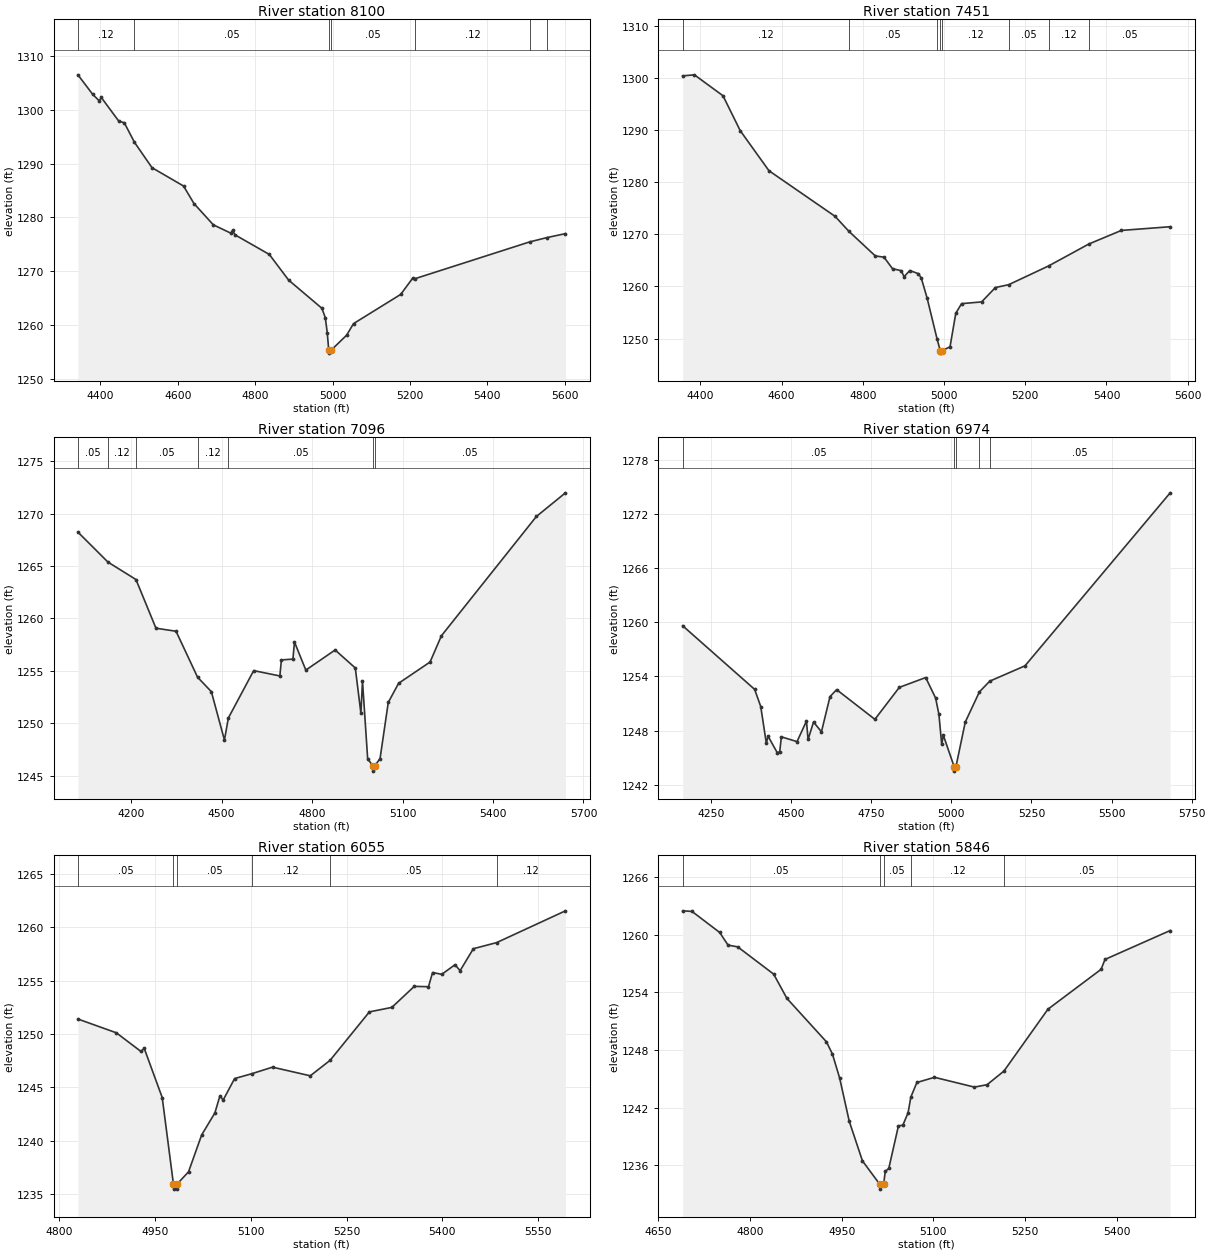
Type RM Length L Ch R = 1,8100,649,649,649
BEGIN DESCRIPTION:
GOLDMINE CREEK 17.0
END DESCRIPTION:
XS GIS Cut Line= 3
      2793412.37     10179820.55      2793233.58     10178965.61
      2792900.89     10178767.98
#Sta/Elev= 30
  4341.7 1306.50  4380.0 1302.86  4397.0 1301.65  4402.1 1302.29  4447.0 1297.92
  4461.7 1297.57  4487.9 1293.95  4533.2 1289.23  4614.9 1285.81  4641.8 1282.55
  4691.7 1278.60  4736.6 1277.06  4741.7 1277.58  4747.7 1276.74  4836.5 1273.09
  4886.5 1268.31  4972.5 1263.07  4981.3 1261.31  4986.4 1258.46  4990.2 1255.23
  4990.6 1254.73  4995.7 1255.23  5036.4 1258.07  5054.2 1260.22  5176.1 1265.65
  5207.5 1268.70  5214.1 1268.60  5509.6 1275.42  5554.0 1276.22  5602.1 1276.96
#Mann=7,-1,0
  4341.7    0.12       0  4487.9    0.05       0  4990.2    0.05       0
  4995.7    0.05       0  5214.1    0.12       0  5509.6    0.05       0
  5554.0    0.12       0
Bank Sta=4990.2,4995.7
Exp/Cntr=0.3,0.1

Type RM Length L Ch R = 1,7451,355,355,355
BEGIN DESCRIPTION:
Mapping XS 19030346
END DESCRIPTION:
XS GIS Cut Line= 3
      2794206.93     10179192.41      2793652.00     10178667.75
      2793215.57     10178655.14
#Sta/Elev= 30
  4356.6 1300.39  4385.5 1300.59  4455.9 1296.58  4498.3 1289.89  4569.1 1282.20
  4731.8 1273.46  4765.9 1270.58  4830.9 1265.86  4852.3 1265.62  4873.3 1263.41
  4894.8 1263.03  4901.7 1261.88  4915.8 1263.06  4936.9 1262.46  4944.1 1261.61
  4958.3 1257.83  4983.1 1249.90  4990.7 1247.72  4991.1 1247.22  4996.3 1247.72
  5014.9 1248.44  5029.1 1254.87  5043.3 1256.71  5092.6 1257.04  5126.6 1259.80
  5159.2 1260.34  5257.8 1263.95  5356.5 1268.14  5436.7 1270.75  5556.9 1271.46
#Mann=8,-1,0
  4356.6    0.12       0  4765.9    0.05       0  4983.1    0.12       0
  4990.7    0.07       0  4996.3    0.12       0  5159.2    0.05       0
  5257.8    0.12       0  5356.5    0.05       0
Bank Sta=4990.7,4996.3
Exp/Cntr=0.3,0.1

Type RM Length L Ch R = 1,7096,122,122,122
BEGIN DESCRIPTION:
GOLDMINE CREEK 16.0
END DESCRIPTION:
XS GIS Cut Line= 3
      2794903.18     10178251.54      2794103.53     10178430.64
      2793326.57     10178609.74
#Sta/Elev= 30
  4023.5 1268.25  4123.3 1265.38  4216.0 1263.72  4282.3 1259.07  4348.9 1258.78
  4420.3 1254.39  4466.0 1253.01  4509.4 1248.39  4522.5 1250.50  4606.4 1255.02
  4693.2 1254.51  4698.3 1256.04  4736.5 1256.12  4741.7 1257.75  4779.3 1255.07
  4876.5 1256.99  4943.4 1255.27  4962.0 1250.94  4967.2 1254.04  4984.4 1246.59
  5002.0 1245.92  5002.5 1245.42  5007.7 1245.92  5025.5 1246.62  5052.7 1251.98
  5087.0 1253.81  5191.3 1255.84  5229.0 1258.35  5543.9 1269.74  5640.3 1272.00
#Mann=7,-1,0
  4023.5    0.05       0  4123.3    0.12       0  4216.0    0.05       0
  4420.3    0.12       0  4522.5    0.05       0  5002.0    0.05       0
  5007.7    0.05       0
Bank Sta=5002,5007.7
Exp/Cntr=0.3,0.1

Type RM Length L Ch R = 1,6974,919,919,919
BEGIN DESCRIPTION:
GOLDMINE CREEK 15.0
END DESCRIPTION:
XS GIS Cut Line= 3
      2794812.30     10178155.70      2793793.29     10178404.35
      2793336.71     10178523.97
#Sta/Elev= 30
  4162.1 1259.61  4386.7 1252.56  4405.7 1250.66  4423.2 1246.58  4428.4 1247.38
  4457.1 1245.55  4464.9 1245.64  4470.1 1247.30  4518.9 1246.77  4548.3 1249.04
  4553.4 1247.01  4570.4 1248.94  4595.1 1247.86  4621.8 1251.76  4642.4 1252.53
  4761.8 1249.24  4838.0 1252.78  4920.3 1253.87  4951.2 1251.60  4961.5 1249.80
  4970.2 1246.47  4975.4 1247.47  5009.0 1244.00  5009.5 1243.50  5014.7 1244.00
  5043.8 1248.94  5088.0 1252.29  5120.1 1253.47  5230.1 1255.17  5683.0 1274.34
#Mann=5,-1,0
  4162.1    0.05       0  5009.0    0.05       0  5014.7    0.05       0
  5088.0    0.12       0  5120.1    0.05       0
Bank Sta=5009,5014.7
Exp/Cntr=0.3,0.1

Type RM Length L Ch R = 1,6055,209,209,209
BEGIN DESCRIPTION:
GOLDMINE CREEK 14.0
END DESCRIPTION:
XS GIS Cut Line= 4
      2794613.07     10178153.20      2794618.12     10178082.53
      2794555.05     10177830.29      2794220.12     10177555.80
#Sta/Elev= 30
  4829.1 1251.39  4889.3 1250.10  4927.9 1248.35  4933.0 1248.64  4961.2 1244.03
  4978.7 1235.95  4979.2 1235.45  4984.4 1235.45  4984.9 1235.95  5002.4 1237.07
  5023.0 1240.53  5043.7 1242.59  5051.6 1244.19  5056.7 1243.80  5074.6 1245.81
  5101.2 1246.26  5134.0 1246.88  5193.2 1246.07  5224.2 1247.52  5285.8 1252.06
  5321.0 1252.48  5356.1 1254.45  5378.4 1254.42  5384.8 1255.75  5399.2 1255.58
  5420.0 1256.48  5427.9 1255.92  5448.7 1257.98  5485.1 1258.55  5593.0 1261.53
#Mann=6,-1,0
  4829.1    0.05       0  4978.7    0.05       0  4984.9    0.05       0
  5101.2    0.12       0  5224.2    0.05       0  5485.1    0.12       0
Bank Sta=4978.7,4984.9
Exp/Cntr=0.3,0.1

Type RM Length L Ch R = 1,5846,220,220,220
BEGIN DESCRIPTION:
GOLDMINE CREEK 13.0
END DESCRIPTION:
XS GIS Cut Line= 3
      2794925.88     10178145.64      2794701.36     10177754.61
      2794426.43     10177542.74
#Sta/Elev= 30
  4689.6 1262.48  4704.9 1262.42  4750.2 1260.23  4763.9 1258.91  4779.7 1258.73
  4838.6 1255.89  4860.2 1253.37  4924.9 1248.85  4934.7 1247.58  4946.5 1245.09
  4962.3 1240.57  4983.9 1236.45  5012.3 1234.01  5012.8 1233.51  5018.5 1234.01
  5021.3 1235.36  5027.0 1235.66  5042.8 1240.10  5050.0 1240.16  5058.6 1241.46
  5063.1 1243.09  5073.0 1244.61  5101.8 1245.15  5167.1 1244.13  5187.9 1244.38
  5215.5 1245.80  5287.5 1252.24  5374.5 1256.39  5380.9 1257.42  5487.6 1260.43
#Mann=5,-1,0
  4689.6    0.05       0  5012.3    0.03       0  5018.5    0.05       0
  5063.1    0.12       0  5215.5    0.05       0
Bank Sta=5012.3,5018.5
Exp/Cntr=0.3,0.1