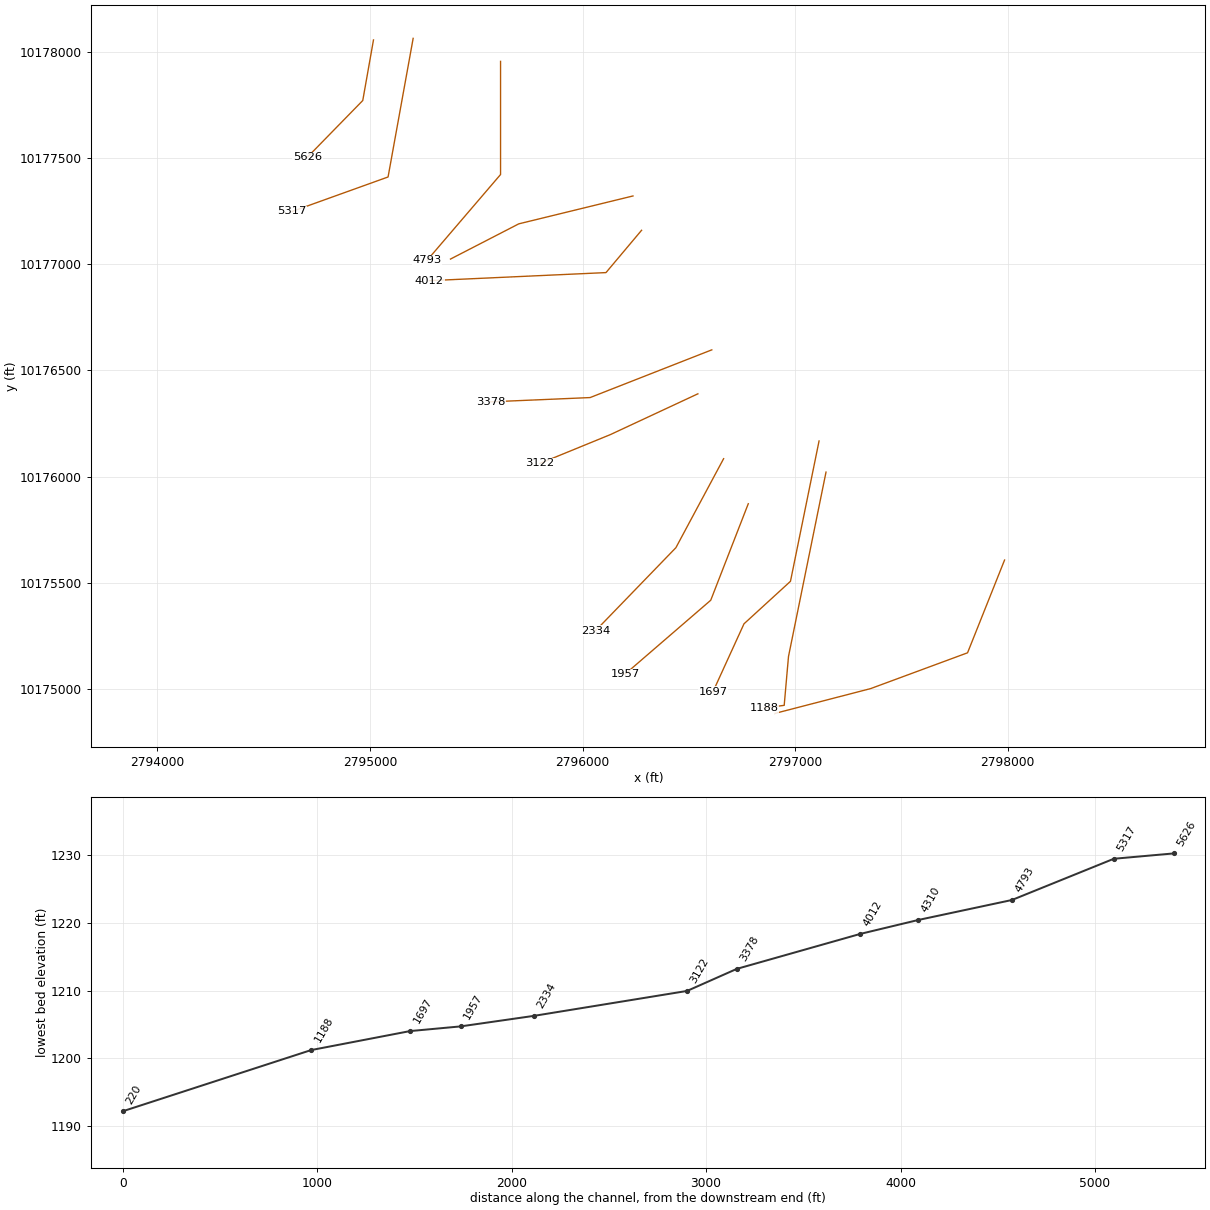
HEC-RAS study GOLDMINE CREEK.prj: GOLDMINE CREEK Base Level Engineering

--- GOLDMINE CREEK.g01 (geometry) --- (continued)

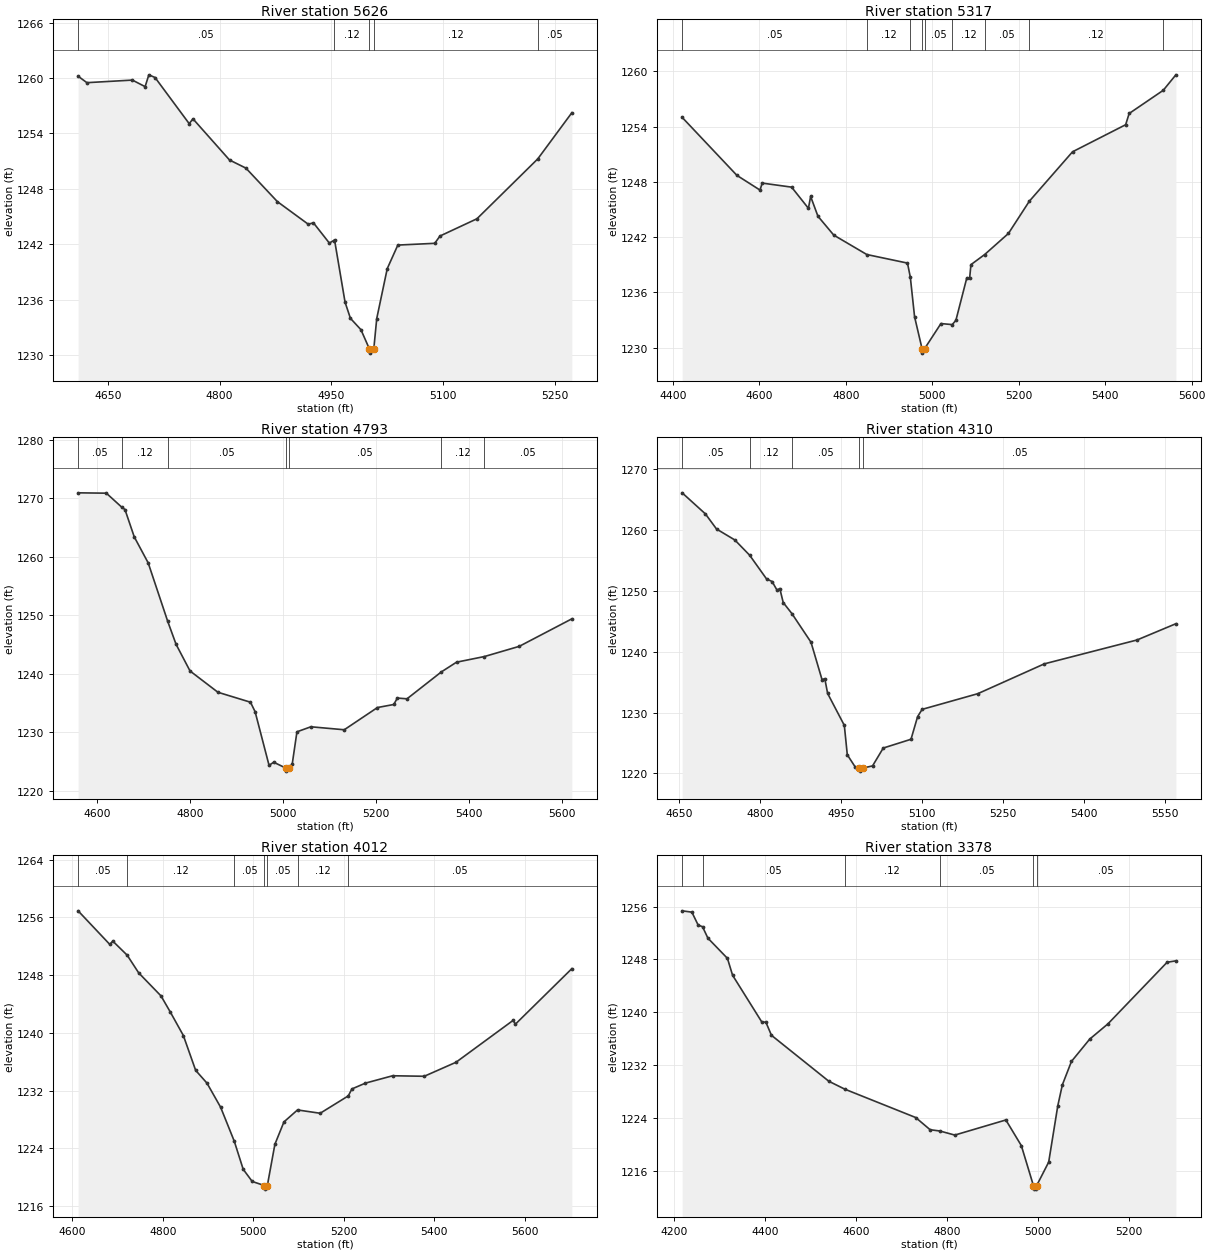
Type RM Length L Ch R = 1,5626,309,309,309
BEGIN DESCRIPTION:
GOLDMINE CREEK 12.0
END DESCRIPTION:
XS GIS Cut Line= 3
      2795016.67     10178054.78      2794966.22     10177769.75
      2794705.65     10177503.08
#Sta/Elev= 30
  4610.1 1260.20  4621.9 1259.50  4682.9 1259.78  4700.0 1259.07  4705.0 1260.35
  4713.3 1260.06  4759.1 1255.06  4764.2 1255.58  4813.2 1251.12  4835.2 1250.24
  4877.4 1246.61  4918.8 1244.16  4925.8 1244.31  4947.1 1242.12  4952.9 1242.39
  4954.1 1242.45  4968.2 1235.71  4975.4 1233.96  4989.5 1232.73  5000.6 1230.69
  5001.1 1230.19  5006.8 1230.69  5010.7 1233.94  5024.8 1239.35  5039.0 1241.90
  5088.5 1242.09  5095.5 1242.88  5145.1 1244.75  5226.7 1251.24  5272.4 1256.24
#Mann=5,-1,0
  4610.1    0.05       0  4952.9    0.12       0  5000.6    0.07       0
  5006.8    0.12       0  5226.7    0.05       0
Bank Sta=5000.6,5006.8
Exp/Cntr=0.3,0.1

Type RM Length L Ch R = 1,5317,524,524,524
BEGIN DESCRIPTION:
GOLDMINE CREEK 11.0
END DESCRIPTION:
XS GIS Cut Line= 3
      2795203.33     10178062.32      2795085.29     10177410.09
      2794633.99     10177247.86
#Sta/Elev= 30
  4421.1 1255.01  4547.8 1248.71  4601.3 1247.11  4606.3 1247.87  4674.4 1247.43
  4713.3 1245.13  4718.4 1246.42  4735.3 1244.27  4771.9 1242.22  4848.4 1240.11
  4942.5 1239.18  4949.1 1237.64  4958.9 1233.35  4976.1 1229.90  4976.6 1229.40
  4982.3 1229.90  5019.9 1232.61  5046.0 1232.50  5054.5 1232.96  5079.8 1237.58
  5086.4 1237.58  5089.3 1239.01  5121.1 1240.11  5176.1 1242.40  5224.4 1245.90
  5324.4 1251.27  5447.3 1254.21  5455.4 1255.43  5534.3 1257.95  5563.5 1259.63
#Mann=9,-1,0
  4421.1    0.05       0  4848.4    0.12       0  4949.1    0.05       0
  4976.1    0.05       0  4982.3    0.05       0  5046.0    0.12       0
  5121.1    0.05       0  5224.4    0.12       0  5534.3    0.05       0
Bank Sta=4976.1,4982.3
Exp/Cntr=0.3,0.1

Type RM Length L Ch R = 1,4793,483,483,483
BEGIN DESCRIPTION:
GOLDMINE CREEK 10.0
END DESCRIPTION:
XS GIS Cut Line= 3
      2795614.50     10177953.89      2795614.50     10177421.64
      2795269.82     10177019.10
#Sta/Elev= 30
  4559.4 1270.90  4620.2 1270.84  4653.9 1268.40  4660.2 1268.05  4680.2 1263.37
  4710.2 1258.92  4752.2 1248.93  4770.2 1245.00  4800.2 1240.45  4860.2 1236.81
  4930.2 1235.11  4940.2 1233.49  4970.2 1224.32  4980.2 1224.85  5006.9 1223.83
  5007.4 1223.33  5013.4 1223.83  5020.2 1224.61  5030.2 1230.05  5060.2 1230.91
  5132.0 1230.40  5203.4 1234.20  5238.5 1234.72  5246.2 1235.82  5267.0 1235.69
  5340.9 1240.29  5373.5 1241.95  5433.7 1242.92  5508.5 1244.66  5621.6 1249.36
#Mann=7,-1,0
  4559.4    0.05       0  4653.9    0.12       0  4752.2    0.05       0
  5006.9    0.05       0  5013.4    0.05       0  5340.9    0.12       0
  5433.7    0.05       0
Bank Sta=5006.9,5013.4
Exp/Cntr=0.3,0.1

Type RM Length L Ch R = 1,4310,298,298,298
BEGIN DESCRIPTION:
GOLDMINE CREEK 9.0
END DESCRIPTION:
XS GIS Cut Line= 3
      2796237.54     10177320.74      2795700.26     10177189.57
      2795379.01     10177023.93
#Sta/Elev= 30
  4656.0 1266.07  4699.1 1262.61  4719.7 1260.13  4753.6 1258.33  4781.1 1255.82
  4812.3 1251.94  4822.6 1251.51  4831.7 1250.10  4836.9 1250.36  4843.2 1248.06
  4859.4 1246.23  4894.7 1241.54  4915.1 1235.40  4920.2 1235.56  4925.5 1233.13
  4956.4 1227.89  4961.9 1223.06  4977.0 1221.00  4984.1 1220.88  4984.6 1220.38
  4990.6 1220.88  5008.7 1221.24  5028.5 1224.17  5079.9 1225.61  5092.1 1229.32
  5100.5 1230.52  5203.5 1233.09  5326.8 1237.99  5498.5 1241.91  5570.5 1244.58
#Mann=5,-1,0
  4656.0    0.05       0  4781.1    0.12       0  4859.4    0.05       0
  4984.1    0.05       0  4990.6    0.05       0
Bank Sta=4984.1,4990.6
Exp/Cntr=0.3,0.1

Type RM Length L Ch R = 1,4012,634,634,634
BEGIN DESCRIPTION:
GOLDMINE CREEK 8.0
END DESCRIPTION:
XS GIS Cut Line= 3
      2796277.91     10177159.30      2796110.56     10176960.27
      2795279.87     10176922.23
#Sta/Elev= 30
  4612.4 1256.92  4682.5 1252.26  4689.1 1252.72  4720.9 1250.77  4746.3 1248.32
  4795.7 1245.12  4816.5 1242.86  4845.1 1239.63  4872.3 1234.80  4897.3 1233.03
  4927.4 1229.70  4957.7 1224.97  4977.4 1221.08  4997.4 1219.39  5024.2 1218.83
  5024.7 1218.33  5030.8 1218.83  5047.5 1224.55  5067.5 1227.65  5097.5 1229.31
  5147.6 1228.85  5209.8 1231.26  5217.7 1232.22  5247.7 1233.03  5307.8 1234.05
  5377.8 1233.98  5447.9 1235.92  5574.2 1241.73  5579.2 1241.20  5704.0 1248.90
#Mann=7,-1,0
  4612.4    0.05       0  4720.9    0.12       0  4957.7    0.05       0
  5024.2    0.05       0  5030.8    0.05       0  5097.5    0.12       0
  5209.8    0.05       0
Bank Sta=5024.2,5030.8
Exp/Cntr=0.3,0.1

Type RM Length L Ch R = 1,3378,256,256,256
BEGIN DESCRIPTION:
GOLDMINE CREEK 7.0
END DESCRIPTION:
XS GIS Cut Line= 3
      2796608.35     10176596.79      2796035.75     10176372.29
      2795566.52     10176352.10
#Sta/Elev= 30
  4218.3 1255.36  4239.7 1255.16  4253.4 1253.21  4263.1 1252.95  4274.9 1251.22
  4317.8 1248.16  4329.1 1245.60  4393.0 1238.55  4402.4 1238.47  4414.5 1236.50
  4540.7 1229.53  4575.9 1228.33  4731.4 1224.04  4763.1 1222.19  4784.4 1222.00
  4817.3 1221.38  4929.5 1223.67  4963.5 1219.78  4990.2 1213.69  4990.7 1213.19
  4996.4 1213.19  4996.9 1213.69  5023.6 1217.29  5043.6 1225.83  5053.6 1228.99
  5073.6 1232.54  5113.7 1235.92  5153.7 1238.23  5283.8 1247.57  5303.0 1247.78
#Mann=6,-1,0
  4218.3    0.12       0  4263.1    0.05       0  4575.9    0.12       0
  4784.4    0.05       0  4990.2    0.03       0  4996.9    0.05       0
Bank Sta=4990.2,4996.9
Exp/Cntr=0.3,0.1

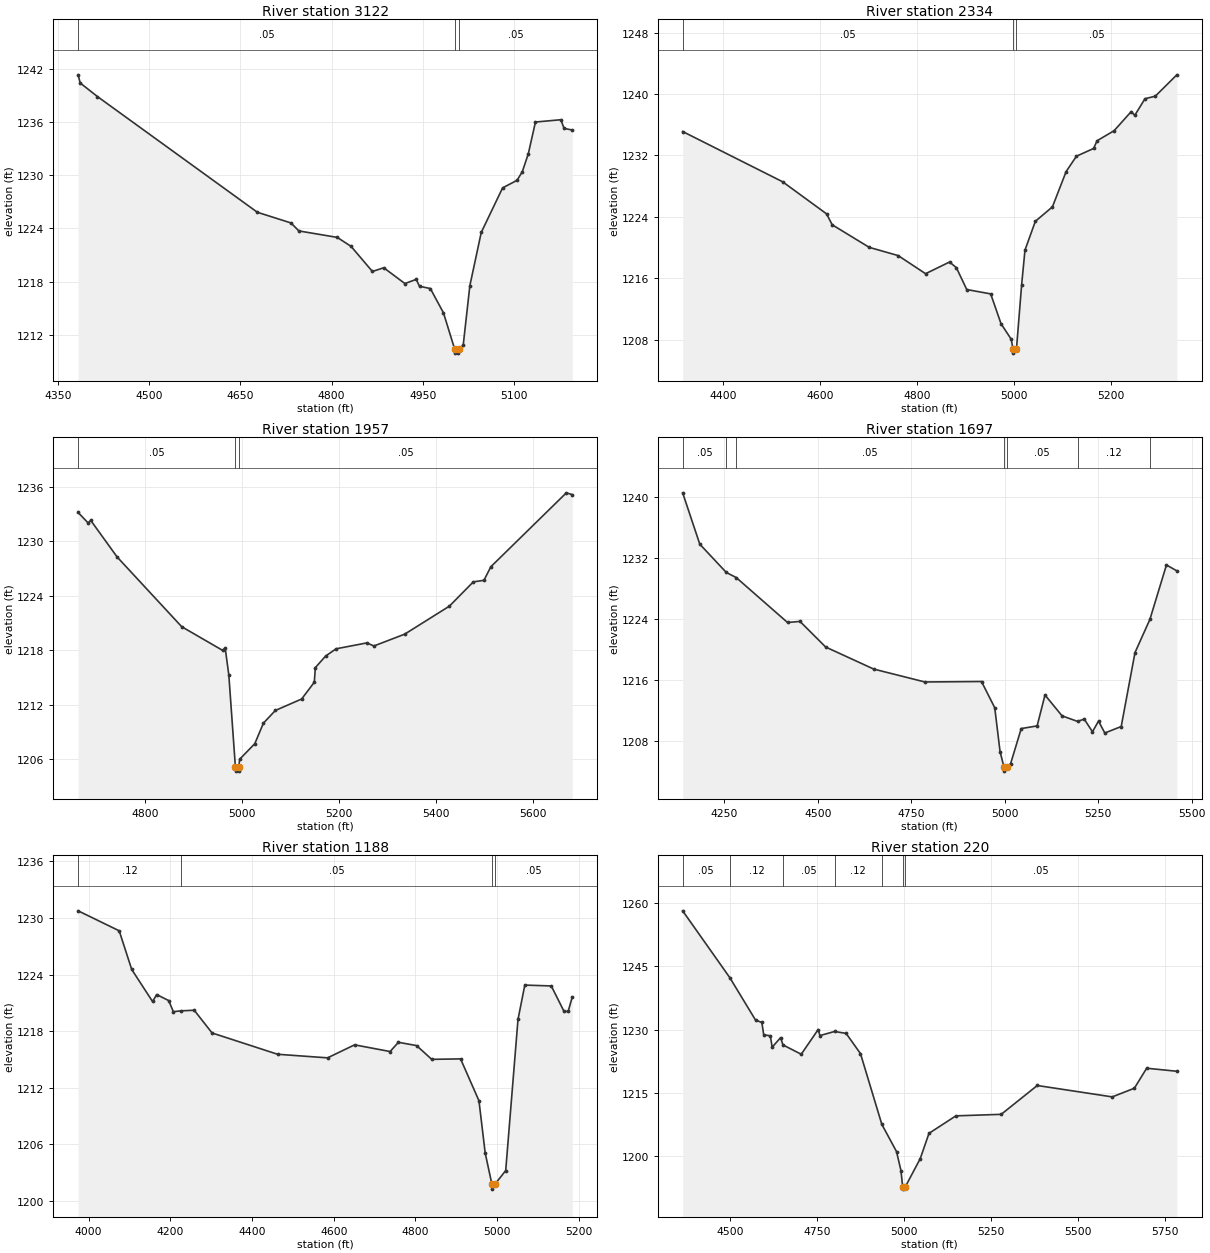
Type RM Length L Ch R = 1,3122,788,788,788
BEGIN DESCRIPTION:
GOLDMINE CREEK 6.0
END DESCRIPTION:
XS GIS Cut Line= 3
      2796542.82     10176389.96      2796131.61     10176198.24
      2795799.62     10176062.42
#Sta/Elev= 30
  4383.2 1241.30  4386.6 1240.38  4415.0 1238.85  4677.9 1225.81  4733.1 1224.61
  4746.1 1223.71  4809.2 1222.98  4831.9 1221.97  4867.0 1219.14  4885.6 1219.56
  4920.4 1217.78  4939.0 1218.25  4944.4 1217.47  4962.2 1217.22  4983.8 1214.48
  5002.0 1210.44  5002.5 1209.94  5008.2 1209.94  5008.7 1210.44  5016.2 1210.80
  5027.2 1217.55  5045.9 1223.54  5081.0 1228.56  5104.7 1229.41  5113.4 1230.38
  5123.3 1232.41  5135.0 1235.98  5176.7 1236.24  5182.1 1235.26  5195.6 1235.08
#Mann=3,-1,0
  4383.2    0.05       0  5002.0    0.05       0  5008.7    0.05       0
Bank Sta=5002,5008.7
Exp/Cntr=0.3,0.1

Type RM Length L Ch R = 1,2334,377,377,377
BEGIN DESCRIPTION:
GOLDMINE CREEK 5.0
END DESCRIPTION:
XS GIS Cut Line= 3
      2796663.86     10176084.73      2796439.35     10175665.99
      2796060.99     10175275.02
#Sta/Elev= 30
  4316.5 1235.12  4522.6 1228.58  4613.3 1224.40  4624.9 1222.98  4701.3 1220.04
  4760.9 1218.97  4817.5 1216.61  4866.9 1218.13  4881.0 1217.40  4902.4 1214.55
  4951.8 1213.98  4973.1 1210.10  4994.2 1208.07  4997.9 1206.77  4998.4 1206.27
  5004.9 1206.77  5015.6 1215.17  5022.5 1219.68  5043.9 1223.43  5079.1 1225.31
  5107.4 1229.91  5128.7 1231.91  5164.0 1232.91  5171.2 1233.92  5206.4 1235.23
  5241.7 1237.72  5248.9 1237.22  5270.0 1239.39  5291.3 1239.72  5335.7 1242.50
#Mann=3,-1,0
  4316.5    0.05       0  4997.9    0.05       0  5004.9    0.05       0
Bank Sta=4997.9,5004.9
Exp/Cntr=0.3,0.1

Type RM Length L Ch R = 1,1957,260,260,260
BEGIN DESCRIPTION:
GOLDMINE CREEK 4.0
END DESCRIPTION:
XS GIS Cut Line= 3
      2796779.89     10175872.83      2796603.31     10175418.79
      2796200.21     10175071.11
#Sta/Elev= 30
  4661.8 1233.16  4682.4 1232.01  4687.8 1232.29  4742.2 1228.27  4875.5 1220.60
  4959.8 1218.00  4965.2 1218.25  4972.7 1215.29  4986.2 1205.22  4986.7 1204.72
  4992.7 1204.72  4993.2 1205.22  4995.1 1206.03  5026.3 1207.74  5044.1 1210.00
  5068.7 1211.39  5122.9 1212.65  5149.0 1214.49  5151.2 1216.10  5172.3 1217.37
  5194.0 1218.17  5257.6 1218.82  5271.9 1218.48  5335.5 1219.78  5427.7 1222.86
  5477.1 1225.53  5499.0 1225.70  5513.2 1227.19  5669.0 1235.32  5681.3 1235.12
#Mann=3,-1,0
  4661.8    0.05       0  4986.2    0.05       0  4993.2    0.05       0
Bank Sta=4986.2,4993.2
Exp/Cntr=0.3,0.1

Type RM Length L Ch R = 1,1697,509,509,509
BEGIN DESCRIPTION:
GOLDMINE CREEK 3.0
END DESCRIPTION:
XS GIS Cut Line= 4
      2797112.87     10176168.00      2796978.40     10175507.84
      2796759.71     10175307.80      2796613.56     10174987.79
#Sta/Elev= 30
  4138.5 1240.52  4184.3 1233.79  4255.2 1230.08  4281.8 1229.41  4419.0 1223.52
  4452.4 1223.66  4521.1 1220.30  4649.6 1217.41  4786.4 1215.72  4937.9 1215.78
  4973.3 1212.34  4987.5 1206.60  4998.1 1204.53  4998.6 1204.03  5005.1 1204.53
  5015.8 1205.02  5044.2 1209.61  5086.7 1209.96  5107.7 1214.01  5153.3 1211.28
  5194.7 1210.55  5212.7 1210.85  5234.7 1209.19  5250.9 1210.59  5267.7 1209.03
  5311.6 1209.88  5348.5 1219.58  5388.3 1223.92  5432.6 1231.06  5460.4 1230.29
#Mann=7,-1,0
  4138.5    0.05       0  4255.2    0.12       0  4281.8    0.05       0
  4998.1    0.03       0  5005.1    0.05       0  5194.7    0.12       0
  5388.3    0.05       0
Bank Sta=4998.1,5005.1
Exp/Cntr=0.3,0.1

Type RM Length L Ch R = 1,1188,968,968,968
BEGIN DESCRIPTION:
GOLDMINE CREEK 2.0
END DESCRIPTION:
XS GIS Cut Line= 4
      2797145.65     10176021.67      2796969.08     10175153.92
      2796948.90     10174924.38      2796855.61     10174911.77
#Sta/Elev= 30
  3974.2 1230.76  4074.8 1228.64  4105.4 1224.54  4156.4 1221.14  4166.6 1221.87
  4195.9 1221.24  4207.4 1220.06  4227.0 1220.15  4258.5 1220.21  4302.2 1217.80
  4462.6 1215.54  4585.0 1215.16  4651.2 1216.54  4738.1 1215.83  4758.5 1216.81
  4803.0 1216.46  4840.1 1215.00  4910.7 1215.05  4955.7 1210.61  4971.0 1205.06
  4987.5 1201.73  4988.0 1201.23  4994.5 1201.73  5021.2 1203.20  5051.3 1219.23
  5068.0 1222.88  5132.8 1222.79  5164.0 1220.09  5174.1 1220.08  5184.3 1221.63
#Mann=4,-1,0
  3974.2    0.12       0  4227.0    0.05       0  4987.5    0.03       0
  4994.5    0.05       0
Bank Sta=4987.5,4994.5
Exp/Cntr=0.3,0.1

Type RM Length L Ch R = 1,220,0,0,0
BEGIN DESCRIPTION:
GOLDMINE CREEK 1.0
END DESCRIPTION:
XS GIS Cut Line= 4
      2797985.64     10175607.97      2797811.59     10175171.58
      2797355.68     10175003.11      2796906.00     10174886.54
#Sta/Elev= 30
  4363.8 1258.13  4499.3 1242.31  4573.6 1232.22  4591.4 1231.71  4596.8 1228.78
  4615.7 1228.54  4621.1 1225.84  4645.3 1228.10  4652.2 1226.37  4704.6 1224.17
  4753.2 1230.01  4758.5 1228.59  4800.4 1229.56  4833.6 1229.11  4874.9 1224.32
  4936.3 1207.56  4978.5 1201.12  4991.2 1196.64  4996.2 1192.73  4996.7 1192.23
  5003.4 1192.73  5046.7 1199.46  5071.8 1205.44  5149.1 1209.58  5279.4 1209.94
  5383.1 1216.77  5598.6 1214.07  5662.1 1216.12  5697.5 1220.86  5784.2 1220.14
#Mann=7,-1,0
  4363.8    0.05       0  4499.3    0.12       0  4652.2    0.05       0
  4800.4    0.12       0  4936.3    0.05       0  4996.2    0.05       0
  5003.4    0.05       0
Bank Sta=4996.2,5003.4
Exp/Cntr=0.3,0.1

Chan Stop Cuts=-1