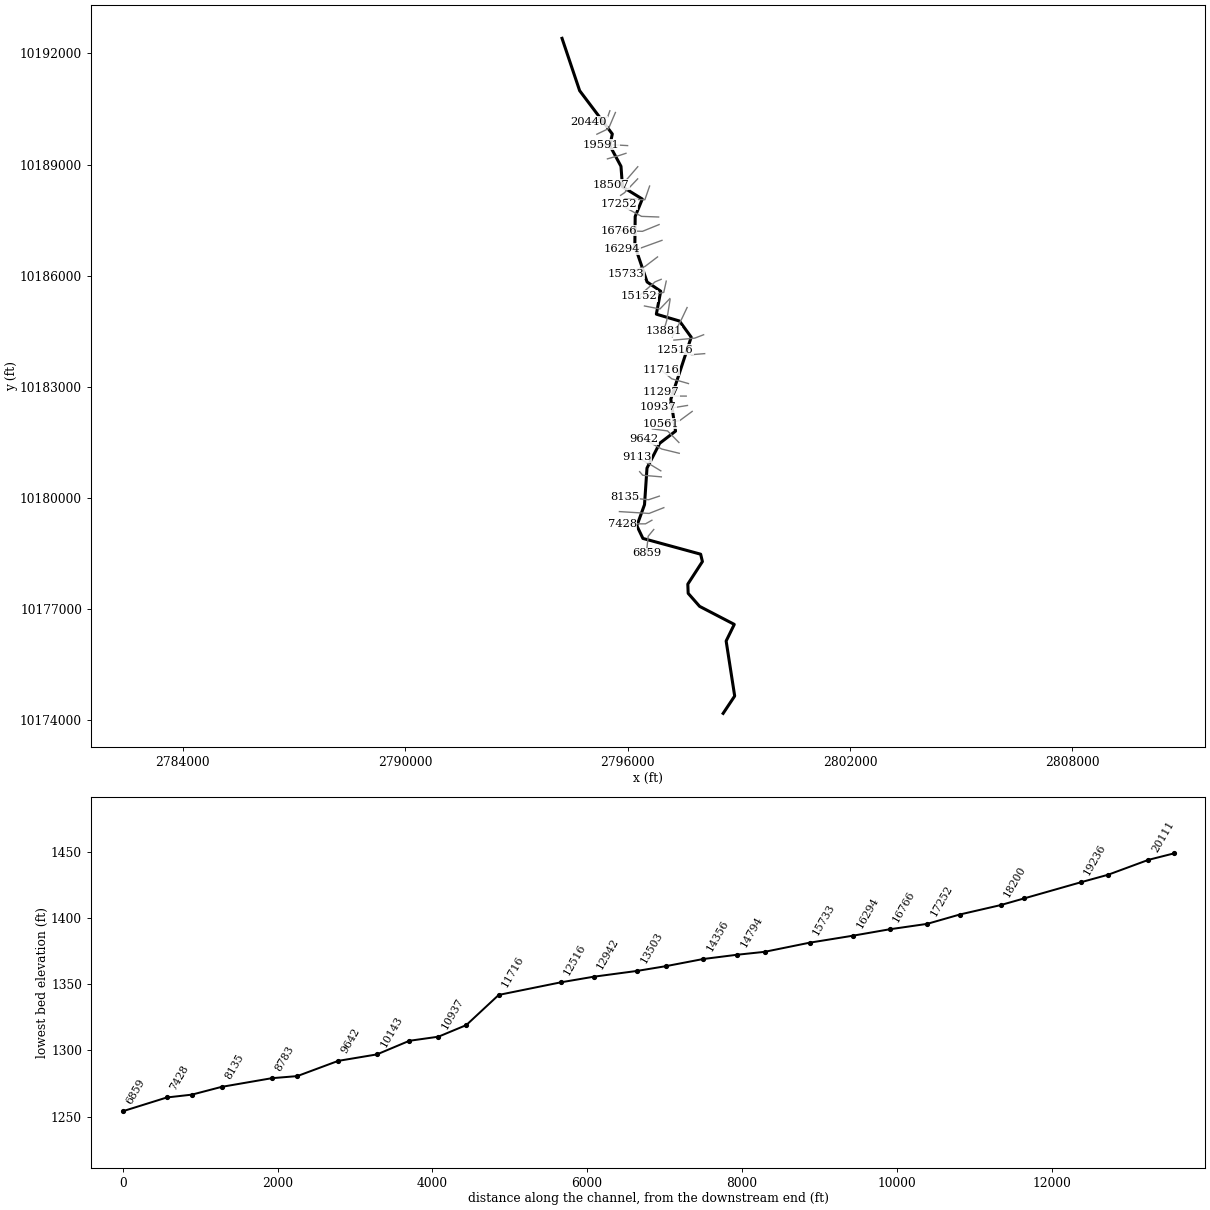
--- GRAPE CREEK.prj (project) ---

Proj Title=GRAPE CREEK Base Level Engineering
Current Plan=p01
Default Exp/Contr=0.3,0.1
English Units
Geom File=g01
Flow File=f01
Plan File=p01
BEGIN DESCRIPTION:
GRAPE CREEK
END DESCRIPTION:

--- GRAPE CREEK.p01 (plan) ---

Plan Title=Multiple Run
Short Identifier=Multiple
Geom File=g01
Flow File=f01
Subcritical Flow
K Sum by GR= 0
Std Step Tol= 0.01
Critical Tol= 0.01
Num of Std Step Trials= 20
Max Error Tol= 0.3
Flow Tol Ratio= 0.001
Split Flow NTrial= 30
Split Flow Tol= 0.02
Split Flow Ratio= 0.02
Log Output Level= 0
Friction Slope Method= 1
Unsteady Friction Slope Method= 2
Unsteady Bridges Friction Slope Method= 1
Parabolic Critical Depth
Global Vel Dist=  1 , 1 , 1
Global Log Level= 0
CheckData=True
Encroach Param= -1, 0, 0, 0
BEGIN DESCRIPTION:
Multiple Run
END DESCRIPTION:

--- GRAPE CREEK.f01 (steady flow) ---

Flow Title=Multiple
Number of Profiles=7
Profile Names=10-year,25-year,50-year,1pct_min,100-year,1pct_plu,500-year
River Rch & RM= GRAPE CREEK,Reach-1,20440
     362     574    1172    1006    1627    2633    2342
River Rch & RM= GRAPE CREEK,Reach-1,17252
     561     920    1768    1400    2475    4376    3534
River Rch & RM= GRAPE CREEK,Reach-1,12942
     766    1283    2598    2008    3694    6797    5296
River Rch & RM= GRAPE CREEK,Reach-1,9642
    1090    1877    3727    2725    5357   10533    7679
River Rch & RM= GRAPE CREEK,Reach-1,2606
    1232    2137    4284    3123    6184   12245    8848
River Rch & RM= GRAPE CREEK,Reach-1,899
    1392    2428    5019    3684    7281   14389   10404
Boundary for River Rch & Prof#=GRAPE CREEK,Reach-1,1
Up Type=0
Dn Type=3
Dn Slope=0.005
Boundary for River Rch & Prof#=GRAPE CREEK,Reach-1,2
Up Type=0
Dn Type=3
Dn Slope=0.005
Boundary for River Rch & Prof#=GRAPE CREEK,Reach-1,3
Up Type=0
Dn Type=3
Dn Slope=0.005
Boundary for River Rch & Prof#=GRAPE CREEK,Reach-1,4
Up Type=0
Dn Type=3
Dn Slope=0.005
Boundary for River Rch & Prof#=GRAPE CREEK,Reach-1,5
Up Type=0
Dn Type=3
Dn Slope=0.005
Boundary for River Rch & Prof#=GRAPE CREEK,Reach-1,6
Up Type=0
Dn Type=3
Dn Slope=0.005
Boundary for River Rch & Prof#=GRAPE CREEK,Reach-1,7
Up Type=0
Dn Type=3
Dn Slope=0.005

--- GRAPE CREEK.g01 (geometry) ---

Geom Title=Existing Conditions

River Reach=GRAPE CREEK,Reach-1
Reach XY= 30
      2794230.50     10192405.00      2794705.75     10190993.00
      2795587.00     10189825.00      2795522.00     10189509.00
      2795821.25     10188952.00      2795861.75     10188400.00
      2796396.25     10188069.00      2796204.50     10187598.00
      2796195.25     10186806.00      2796525.25     10185832.00
      2796893.25     10185582.00      2796775.25     10184963.00
      2797399.25     10184778.00      2797716.25     10184342.00
      2797165.50     10182666.00      2797293.25     10181807.00
      2796865.00     10181479.00      2796523.00     10180810.00
      2796456.00     10179823.00      2796249.50     10179254.00
      2796413.00     10178912.00      2797970.50     10178487.00
      2798018.25     10178288.00      2797624.50     10177680.00
      2797634.00     10177431.00      2797942.75     10177079.00
      2798878.25     10176593.00      2798658.50     10176144.00
      2798889.00     10174660.00      2798577.75     10174192.00

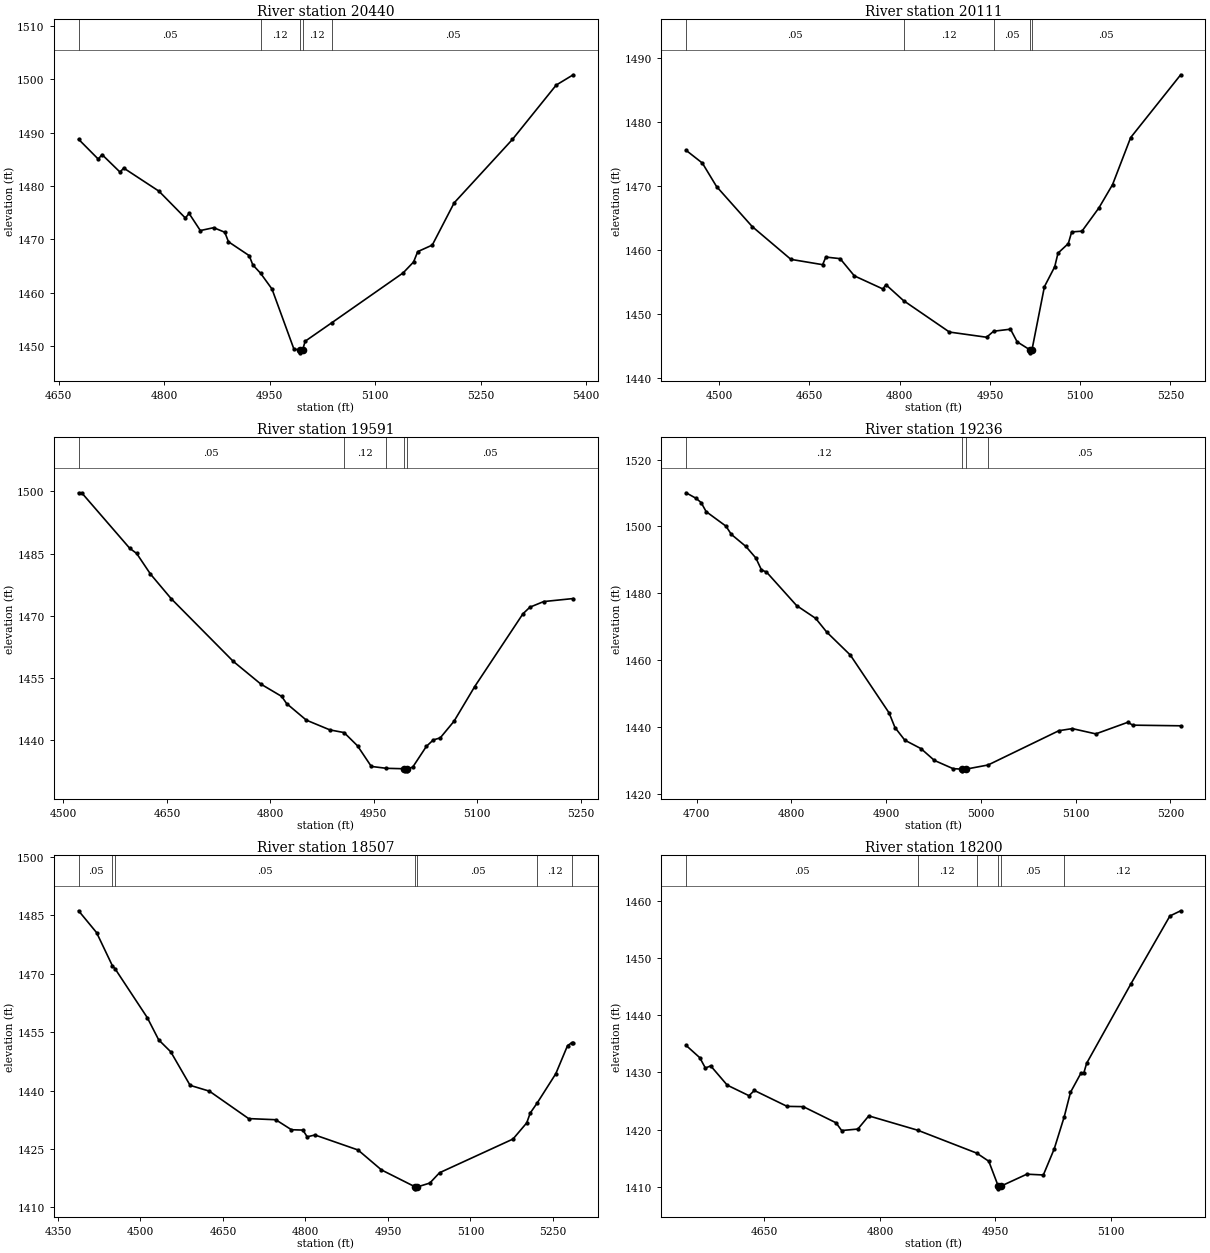
Type RM Length L Ch R = 1,20440,329,329,329
BEGIN DESCRIPTION:
GRAPE CREEK 46.0
END DESCRIPTION:
XS GIS Cut Line= 3
      2795521.26     10190450.87      2795463.58     10190287.18
      2794952.32     10190148.46
#Sta/Elev= 30
  4678.2 1488.78  4706.2 1485.06  4711.5 1485.92  4737.1 1482.63  4742.4 1483.38
  4792.5 1479.05  4830.0 1474.02  4835.3 1474.88  4851.3 1471.67  4870.3 1472.21
  4886.1 1471.35  4891.3 1469.57  4920.8 1466.97  4925.9 1465.24  4936.9 1463.68
  4953.2 1460.71  4984.3 1449.48  4992.6 1449.25  4992.9 1448.75  4996.6 1449.25
  5000.4 1450.93  5038.0 1454.37  5139.7 1463.74  5154.5 1465.78  5160.4 1467.72
  5181.1 1468.95  5212.2 1476.86  5295.1 1488.76  5357.3 1498.94  5381.5 1500.87
#Mann=5,-1,0
  4678.2    0.05       0  4936.9    0.12       0  4992.6    0.07       0
  4996.6    0.12       0  5038.0    0.05       0
Bank Sta=4992.6,4996.6
Exp/Cntr=0.3,0.1

Type RM Length L Ch R = 1,20111,520,520,520
BEGIN DESCRIPTION:
GRAPE CREEK 45.0
END DESCRIPTION:
XS GIS Cut Line= 3
      2795670.88     10190404.06      2795485.40     10189969.20
      2795170.78     10189818.06
#Sta/Elev= 30
  4445.2 1475.56  4472.3 1473.56  4495.9 1469.89  4555.0 1463.64  4619.4 1458.50
  4672.1 1457.67  4677.5 1458.86  4701.2 1458.61  4724.8 1455.92  4772.0 1453.88
  4777.4 1454.53  4806.5 1452.05  4882.8 1447.13  4944.5 1446.32  4956.2 1447.26
  4984.2 1447.58  4995.3 1445.60  5016.0 1444.38  5016.2 1443.88  5020.0 1444.38
  5040.6 1454.23  5057.7 1457.34  5063.2 1459.48  5080.3 1460.97  5085.9 1462.79
  5103.0 1462.91  5131.2 1466.56  5153.8 1470.19  5183.9 1477.55  5267.0 1487.37
#Mann=5,-1,0
  4445.2    0.05       0  4806.5    0.12       0  4956.2    0.05       0
  5016.0    0.05       0  5020.0    0.05       0
Bank Sta=5016,5020
Exp/Cntr=0.3,0.1

Type RM Length L Ch R = 1,19591,355,355,355
BEGIN DESCRIPTION:
GRAPE CREEK 44.0
END DESCRIPTION:
XS GIS Cut Line= 3
      2795999.77     10189510.94      2795669.33     10189529.64
      2795282.80     10189531.20
#Sta/Elev= 30
  4521.9 1499.64  4526.4 1499.64  4596.1 1486.26  4606.1 1485.03  4626.2 1480.05
  4656.2 1474.13  4746.3 1459.02  4786.4 1453.54  4816.5 1450.58  4823.6 1448.87
  4852.2 1444.87  4886.5 1442.51  4907.0 1441.87  4926.5 1438.68  4946.5 1433.71
  4968.4 1433.26  4994.5 1433.15  4994.8 1432.65  4998.3 1432.65  4998.5 1433.15
  5006.5 1433.52  5026.5 1438.57  5036.5 1440.10  5046.5 1440.59  5066.5 1444.60
  5096.5 1452.95  5166.5 1470.49  5176.5 1472.07  5196.5 1473.43  5239.4 1474.16
#Mann=5,-1,0
  4521.9    0.05       0  4907.0    0.12       0  4968.4    0.05       0
  4994.5    0.05       0  4998.5    0.05       0
Bank Sta=4994.5,4998.5
Exp/Cntr=0.3,0.1

Type RM Length L Ch R = 1,19236,729,729,729
BEGIN DESCRIPTION:
GRAPE CREEK 43.0
END DESCRIPTION:
XS GIS Cut Line= 3
      2795955.71     10189303.12      2795790.91     10189249.07
      2795455.71     10189153.12
#Sta/Elev= 30
  4688.8 1510.07  4699.3 1508.43  4704.7 1507.15  4710.0 1504.44  4730.9 1500.10
  4736.6 1497.63  4752.0 1494.01  4762.5 1490.56  4768.4 1487.00  4773.7 1486.37
  4805.5 1476.34  4825.6 1472.52  4837.3 1468.41  4862.2 1461.54  4903.1 1444.25
  4909.3 1439.88  4919.7 1436.09  4936.8 1433.56  4950.9 1430.04  4970.6 1427.58
  4980.1 1427.42  4980.3 1426.92  4984.1 1427.42  5007.6 1428.67  5082.3 1438.92
  5096.5 1439.55  5121.3 1437.97  5155.1 1441.44  5160.3 1440.58  5210.9 1440.39
#Mann=4,-1,0
  4688.8    0.12       0  4980.1    0.07       0  4984.1    0.12       0
  5007.6    0.05       0
Bank Sta=4980.1,4984.1
Exp/Cntr=0.3,0.1

Type RM Length L Ch R = 1,18507,307,307,307
BEGIN DESCRIPTION:
GRAPE CREEK 42.0
END DESCRIPTION:
XS GIS Cut Line= 3
      2796274.14     10188940.48      2795977.96     10188597.53
      2795555.71     10188453.12
#Sta/Elev= 30
  4387.6 1486.20  4420.3 1480.60  4449.2 1472.04  4453.8 1471.34  4512.5 1458.76
  4533.3 1453.04  4555.2 1449.98  4590.4 1441.37  4625.5 1439.87  4696.8 1432.83
  4746.1 1432.54  4774.6 1429.97  4795.5 1429.88  4803.2 1428.15  4817.4 1428.62
  4895.7 1424.77  4938.3 1419.65  4999.7 1415.29  4999.9 1414.79  5003.7 1415.29
  5026.2 1416.27  5043.9 1418.92  5177.5 1427.58  5202.5 1431.74  5208.8 1434.25
  5222.0 1436.95  5255.3 1444.35  5276.7 1451.58  5283.9 1452.26  5287.0 1452.31
#Mann=7,-1,0
  4387.6    0.05       0  4449.2    0.12       0  4453.8    0.05       0
  4999.7    0.05       0  5003.7    0.05       0  5222.0    0.12       0
  5283.9    0.05       0
Bank Sta=4999.7,5003.7
Exp/Cntr=0.3,0.1

Type RM Length L Ch R = 1,18200,527,527,527
BEGIN DESCRIPTION:
GRAPE CREEK 41.0
END DESCRIPTION:
XS GIS Cut Line= 3
      2796271.00     10188613.12      2795915.61     10188239.02
      2795811.18     10188168.88
#Sta/Elev= 30
  4548.5 1434.73  4566.3 1432.58  4573.6 1430.77  4580.5 1431.15  4601.9 1427.79
  4630.2 1425.94  4637.1 1426.86  4679.6 1424.08  4700.6 1424.03  4743.1 1421.21
  4750.4 1419.86  4771.4 1420.12  4785.6 1422.42  4849.2 1419.91  4925.6 1415.92
  4941.3 1414.50  4953.5 1410.18  4953.7 1409.68  4957.5 1410.18  4990.7 1412.24
  5012.1 1412.10  5026.2 1416.65  5039.2 1422.26  5047.3 1426.53  5060.8 1429.86
  5064.5 1429.86  5068.3 1431.61  5125.3 1445.37  5176.3 1457.32  5190.3 1458.23
#Mann=6,-1,0
  4548.5    0.05       0  4849.2    0.12       0  4925.6    0.05       0
  4953.5    0.05       0  4957.5    0.05       0  5039.2    0.12       0
Bank Sta=4953.5,4957.5
Exp/Cntr=0.3,0.1

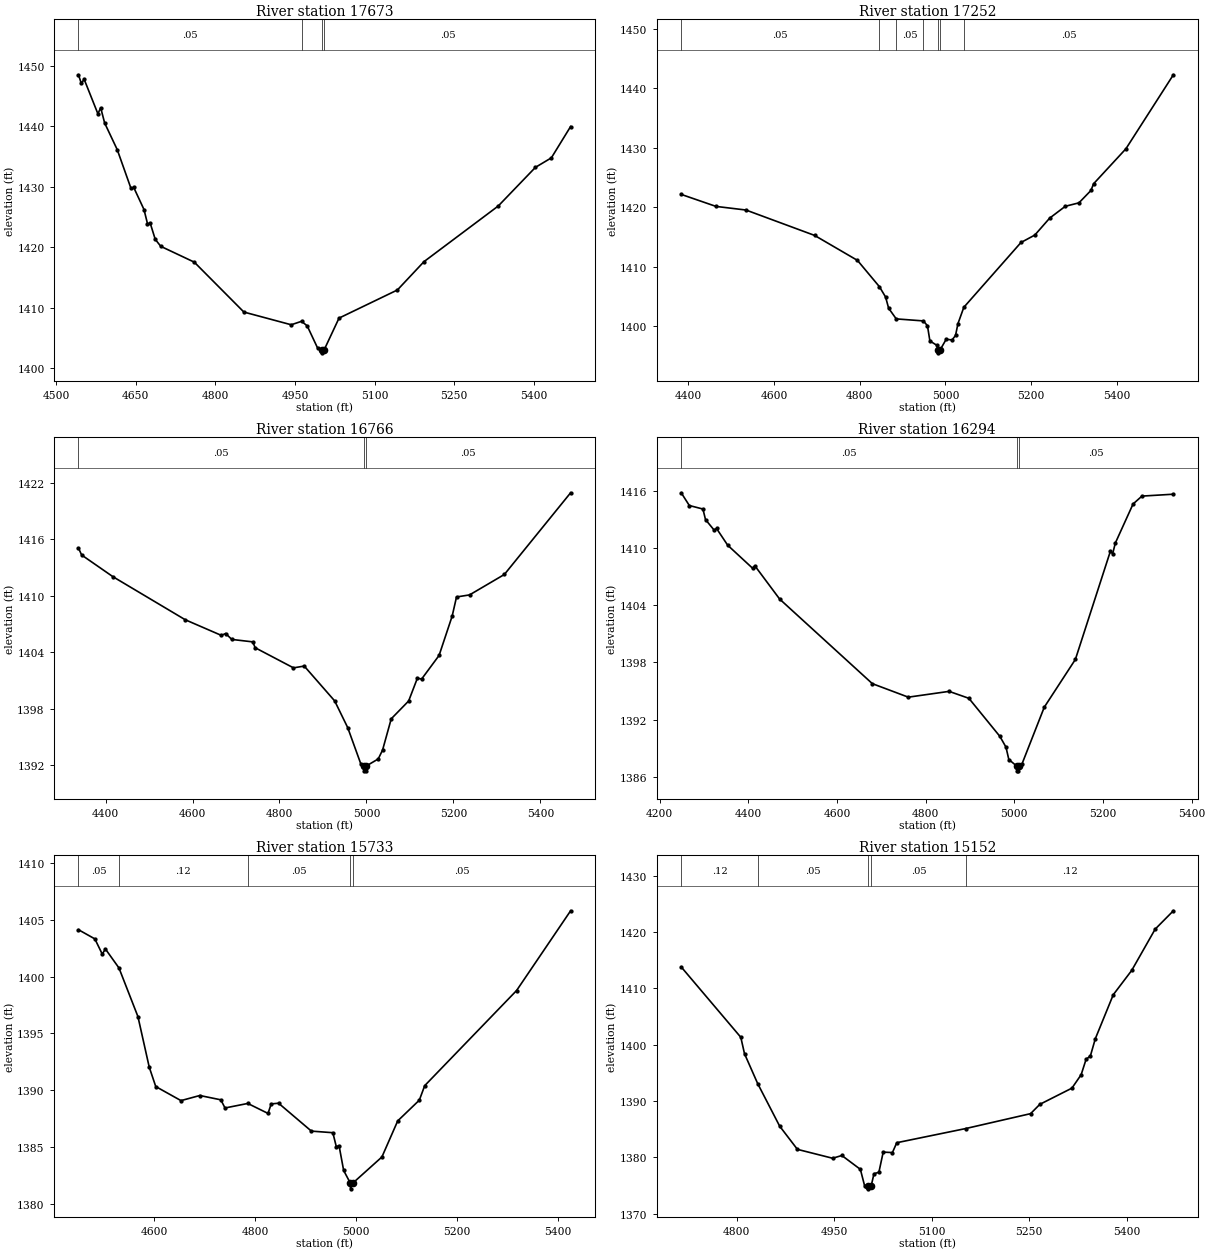
Type RM Length L Ch R = 1,17673,421,421,421
BEGIN DESCRIPTION:
GRAPE CREEK 40.0
END DESCRIPTION:
XS GIS Cut Line= 3
      2796593.65     10188419.82      2796465.84     10188050.42
      2795929.39     10188067.52
#Sta/Elev= 30
  4542.0 1448.54  4547.4 1447.10  4552.7 1447.80  4578.6 1442.10  4583.9 1443.08
  4591.4 1440.56  4615.1 1436.16  4640.9 1429.78  4646.2 1429.91  4665.5 1426.27
  4672.1 1423.93  4677.4 1423.97  4686.7 1421.34  4697.2 1420.18  4760.3 1417.57
  4853.8 1409.32  4943.0 1407.22  4962.5 1407.79  4973.1 1407.04  4993.1 1403.30
  5001.1 1403.08  5001.3 1402.58  5005.1 1403.08  5033.1 1408.32  5143.1 1412.97
  5193.2 1417.65  5333.2 1426.85  5403.3 1433.24  5433.3 1434.81  5469.6 1439.99
#Mann=4,-1,0
  4542.0    0.05       0  4962.5    0.12       0  5001.1    0.07       0
  5005.1    0.05       0
Bank Sta=5001.1,5005.1
Exp/Cntr=0.3,0.1

Type RM Length L Ch R = 1,17252,486,486,486
BEGIN DESCRIPTION:
GRAPE CREEK 39.0
END DESCRIPTION:
XS GIS Cut Line= 3
      2796836.83     10187584.36      2796375.43     10187601.51
      2795772.18     10187930.41
#Sta/Elev= 30
  4383.2 1422.17  4464.4 1420.15  4534.4 1419.54  4694.6 1415.27  4794.6 1411.07
  4845.8 1406.65  4860.2 1404.92  4867.4 1403.02  4885.1 1401.23  4948.4 1400.89
  4958.0 1400.08  4963.7 1397.52  4979.8 1396.79  4983.5 1396.02  4983.7 1395.52
  4987.6 1396.02  5001.7 1397.80  5015.5 1397.69  5023.5 1398.44  5029.2 1400.43
  5042.9 1403.18  5176.3 1414.08  5208.6 1415.33  5243.3 1418.18  5279.8 1420.17
  5311.6 1420.75  5339.6 1422.83  5345.8 1423.96  5421.3 1429.85  5532.0 1442.29
#Mann=7,-1,0
  4383.2    0.05       0  4845.8    0.12       0  4885.1    0.05       0
  4948.4    0.12       0  4983.5    0.07       0  4987.6    0.12       0
  5042.9    0.05       0
Bank Sta=4983.5,4987.6
Exp/Cntr=0.3,0.1

Type RM Length L Ch R = 1,16766,472,472,472
BEGIN DESCRIPTION:
GRAPE CREEK 38.0
END DESCRIPTION:
XS GIS Cut Line= 3
      2796849.24     10187380.15      2796400.37     10187197.80
      2795753.37     10187217.59
#Sta/Elev= 30
  4337.7 1415.09  4345.0 1414.35  4417.1 1412.04  4583.3 1407.47  4666.3 1405.81
  4676.1 1406.01  4690.4 1405.38  4738.6 1405.12  4744.0 1404.50  4832.2 1402.36
  4856.9 1402.55  4926.9 1398.85  4956.9 1396.01  4987.0 1392.16  4994.9 1391.92
  4995.2 1391.42  4998.8 1391.42  4999.0 1391.92  5027.0 1392.68  5037.0 1393.62
  5057.0 1396.95  5097.0 1398.84  5117.0 1401.25  5127.0 1401.18  5167.0 1403.68
  5197.1 1407.86  5207.1 1409.89  5237.1 1410.11  5317.1 1412.28  5469.5 1420.96
#Mann=3,-1,0
  4337.7    0.05       0  4994.9    0.05       0  4999.0    0.05       0
Bank Sta=4994.9,4999
Exp/Cntr=0.3,0.1

Type RM Length L Ch R = 1,16294,561,561,561
BEGIN DESCRIPTION:
GRAPE CREEK 37.0
END DESCRIPTION:
XS GIS Cut Line= 3
      2796927.19     10186954.63      2796342.70     10186742.65
      2795854.86     10186722.39
#Sta/Elev= 30
  4248.6 1415.85  4266.9 1414.51  4297.6 1414.14  4303.4 1413.03  4322.9 1411.92
  4328.2 1412.10  4353.5 1410.33  4409.4 1407.92  4414.7 1408.17  4470.6 1404.67
  4679.7 1395.77  4760.8 1394.35  4852.8 1394.96  4897.4 1394.23  4967.4 1390.22
  4981.1 1389.09  4987.5 1387.79  5005.4 1387.10  5005.7 1386.60  5009.3 1386.60
  5009.5 1387.10  5017.5 1387.36  5067.5 1393.30  5137.6 1398.32  5216.7 1409.72
  5221.7 1409.44  5227.7 1410.56  5267.7 1414.67  5287.7 1415.50  5358.6 1415.70
#Mann=3,-1,0
  4248.6    0.05       0  5005.4    0.05       0  5009.5    0.05       0
Bank Sta=5005.4,5009.5
Exp/Cntr=0.3,0.1

Type RM Length L Ch R = 1,15733,581,581,581
BEGIN DESCRIPTION:
GRAPE CREEK 36.0
END DESCRIPTION:
XS GIS Cut Line= 3
      2796807.23     10186507.31      2796467.39     10186248.54
      2795955.69     10186053.11
#Sta/Elev= 30
  4449.8 1404.15  4482.3 1403.34  4496.9 1402.00  4503.2 1402.45  4530.0 1400.78
  4567.6 1396.49  4590.0 1392.03  4602.9 1390.32  4652.9 1389.08  4690.2 1389.53
  4731.8 1389.15  4740.1 1388.43  4785.2 1388.83  4825.3 1387.95  4831.6 1388.79
  4846.2 1388.85  4911.2 1386.39  4953.7 1386.25  4960.6 1385.01  4966.0 1385.11
  4975.1 1382.92  4988.4 1381.80  4988.7 1381.30  4993.1 1381.80  5050.9 1384.11
  5082.2 1387.29  5125.0 1389.12  5135.7 1390.40  5317.7 1398.79  5424.7 1405.82
#Mann=5,-1,0
  4449.8    0.05       0  4530.0    0.12       0  4785.2    0.05       0
  4988.4    0.05       0  4993.1    0.05       0
Bank Sta=4988.4,4993.1
Exp/Cntr=0.3,0.1

Type RM Length L Ch R = 1,15152,358,358,358
BEGIN DESCRIPTION:
GRAPE CREEK 35.0
END DESCRIPTION:
XS GIS Cut Line= 3
      2796905.67     10185903.11      2796740.26     10185834.53
      2796305.67     10185453.10
#Sta/Elev= 30
  4714.7 1413.80  4806.4 1401.31  4812.1 1398.39  4832.4 1393.08  4866.2 1385.53
  4893.5 1381.41  4947.7 1379.83  4961.9 1380.32  4990.4 1377.86  4997.0 1374.90
  5002.2 1374.90  5002.6 1374.40  5007.0 1374.90  5011.3 1377.08  5018.9 1377.35
  5025.5 1380.92  5039.7 1380.84  5046.4 1382.59  5152.3 1385.10  5252.3 1387.75
  5266.5 1389.40  5315.9 1392.28  5330.1 1394.66  5337.7 1397.40  5344.3 1397.99
  5351.9 1401.05  5379.5 1408.86  5407.9 1413.18  5444.0 1420.51  5472.0 1423.77
#Mann=5,-1,0
  4714.7    0.12       0  4832.4    0.05       0  5002.2    0.05       0
  5007.0    0.05       0  5152.3    0.12       0
Bank Sta=5002.2,5007
Exp/Cntr=0.3,0.1

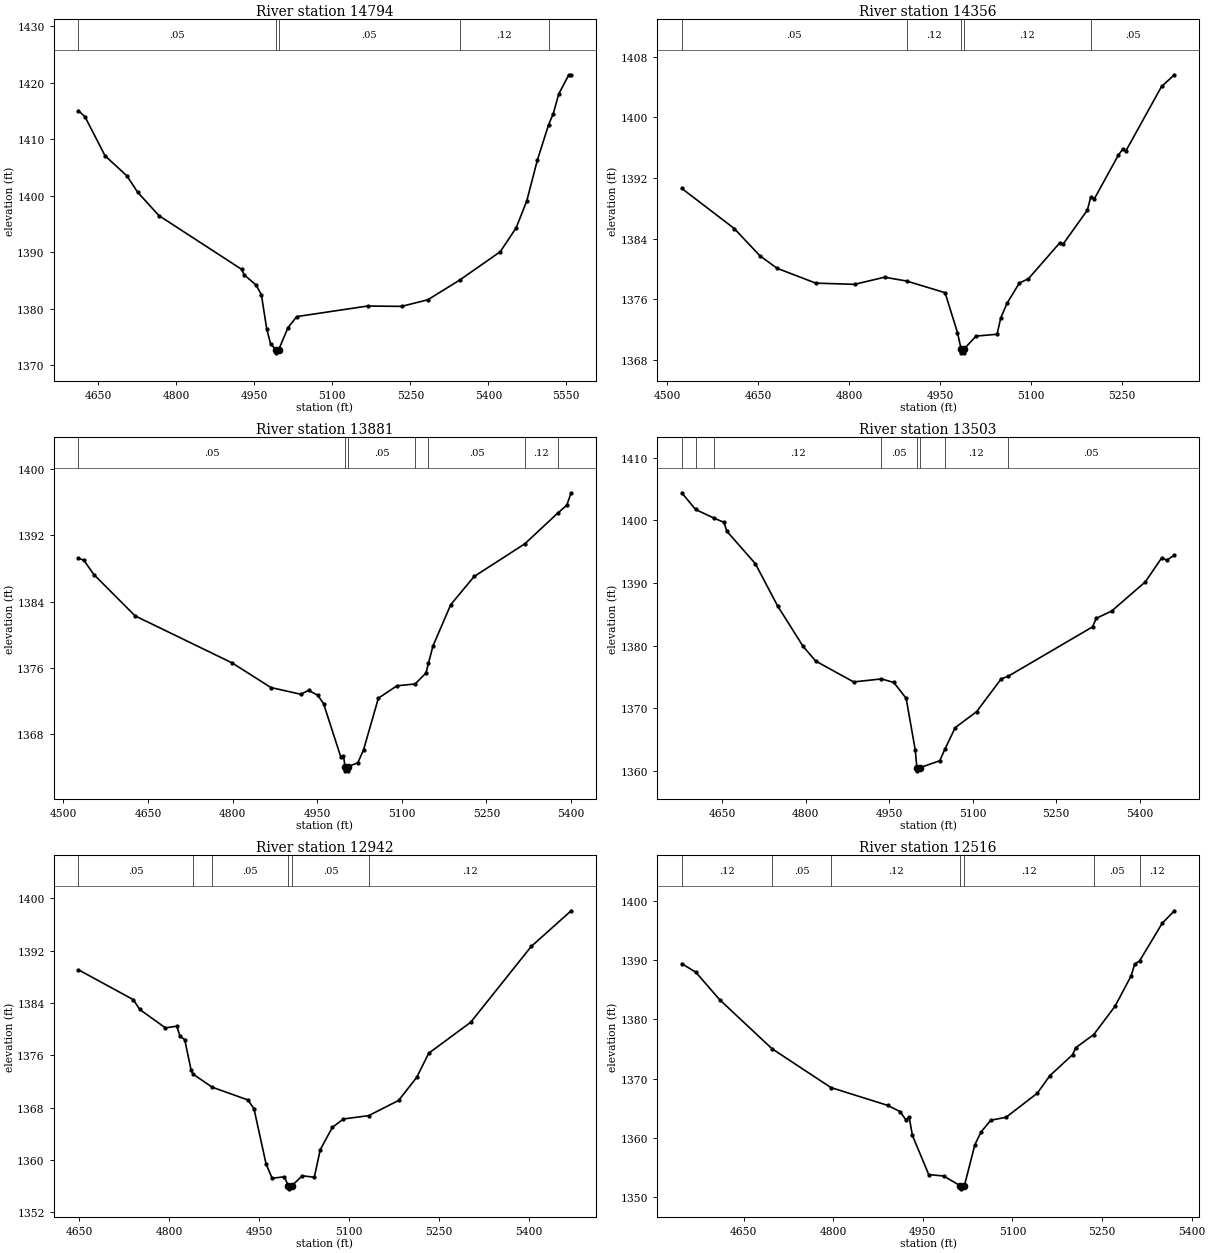
Type RM Length L Ch R = 1,14794,438,438,438
BEGIN DESCRIPTION:
GRAPE CREEK 34.0
END DESCRIPTION:
XS GIS Cut Line= 3
      2797042.56     10185854.15      2796975.54     10185550.23
      2796352.02     10185422.41
#Sta/Elev= 30
  4611.6 1415.01  4624.2 1413.93  4662.7 1407.04  4704.8 1403.48  4725.3 1400.61
  4766.3 1396.46  4925.3 1386.96  4930.6 1385.95  4953.3 1384.18  4963.5 1382.44
  4973.7 1376.42  4981.0 1373.81  4991.7 1372.68  4992.1 1372.18  4996.5 1372.68
  5014.5 1376.61  5031.4 1378.59  5167.7 1380.46  5233.1 1380.40  5283.5 1381.56
  5344.7 1385.04  5422.9 1390.06  5453.5 1394.28  5473.9 1399.03  5494.3 1406.25
  5515.8 1412.49  5524.9 1414.48  5535.6 1418.00  5554.9 1421.37  5559.3 1421.37
#Mann=5,-1,0
  4611.6    0.05       0  4991.7    0.05       0  4996.5    0.05       0
  5344.7    0.12       0  5515.8    0.05       0
Bank Sta=4991.7,4996.5
Exp/Cntr=0.3,0.1

Type RM Length L Ch R = 1,14356,475,475,475
BEGIN DESCRIPTION:
GRAPE CREEK 33.0
END DESCRIPTION:
XS GIS Cut Line= 3
      2797139.21     10185381.89      2796872.66     10185102.88
      2796454.92     10185183.93
#Sta/Elev= 30
  4524.4 1390.63  4610.9 1385.34  4653.3 1381.73  4681.6 1380.09  4745.2 1378.14
  4809.0 1377.98  4858.4 1378.92  4894.6 1378.42  4958.1 1376.88  4978.5 1371.63
  4984.5 1369.45  4984.9 1368.95  4989.0 1368.95  4989.3 1369.45  5009.1 1371.16
  5043.7 1371.40  5049.8 1373.54  5060.0 1375.46  5080.4 1378.15  5095.4 1378.72
  5147.2 1383.47  5152.2 1383.25  5192.4 1387.76  5198.2 1389.52  5204.0 1389.26
  5243.3 1394.99  5250.6 1395.79  5255.7 1395.54  5314.7 1404.07  5335.8 1405.61
#Mann=5,-1,0
  4524.4    0.05       0  4894.6    0.12       0  4984.5    0.07       0
  4989.3    0.12       0  5198.2    0.05       0
Bank Sta=4984.5,4989.3
Exp/Cntr=0.3,0.1

Type RM Length L Ch R = 1,13881,378,378,378
BEGIN DESCRIPTION:
GRAPE CREEK 32.0
END DESCRIPTION:
XS GIS Cut Line= 3
      2797145.43     10185352.25      2797055.03     10184791.14
      2796969.29     10184498.07
#Sta/Elev= 30
  4526.6 1389.20  4535.9 1388.99  4553.8 1387.26  4627.0 1382.28  4799.2 1376.61
  4867.9 1373.65  4920.8 1372.84  4934.8 1373.31  4951.1 1372.71  4961.3 1371.70
  4991.6 1365.33  4996.6 1365.46  4999.3 1364.12  4999.7 1363.62  5003.9 1363.62
  5004.3 1364.12  5022.0 1364.59  5032.2 1366.16  5058.5 1372.37  5091.4 1373.86
  5123.6 1374.08  5142.9 1375.40  5147.2 1376.56  5155.4 1378.67  5186.8 1383.63
  5228.3 1387.02  5318.3 1390.96  5377.0 1394.68  5392.6 1395.60  5400.3 1397.10
#Mann=7,-1,0
  4526.6    0.05       0  4999.3    0.05       0  5004.3    0.05       0
  5123.6    0.12       0  5147.2    0.05       0  5318.3    0.12       0
  5377.0    0.05       0
Bank Sta=4999.3,5004.3
Exp/Cntr=0.3,0.1

Type RM Length L Ch R = 1,13503,561,561,561
BEGIN DESCRIPTION:
GRAPE CREEK 31.0
END DESCRIPTION:
XS GIS Cut Line= 3
      2797605.25     10185141.83      2797461.86     10184839.46
      2797205.70     10184353.15
#Sta/Elev= 30
  4577.8 1404.41  4602.6 1401.74  4636.0 1400.35  4653.4 1399.69  4658.9 1398.25
  4709.9 1393.08  4749.9 1386.32  4795.4 1379.89  4818.1 1377.52  4886.3 1374.18
  4936.3 1374.66  4958.5 1374.09  4980.6 1371.56  4996.9 1363.32  4999.9 1360.47
  5000.4 1359.97  5005.2 1360.47  5041.0 1361.59  5049.9 1363.39  5068.7 1366.88
  5107.1 1369.43  5151.2 1374.67  5163.6 1375.08  5315.2 1382.98  5321.8 1384.35
  5349.4 1385.50  5409.9 1390.17  5439.5 1394.03  5448.3 1393.63  5462.1 1394.44
#Mann=8,-1,0
  4577.8    0.12       0  4602.6    0.05       0  4636.0    0.12       0
  4936.3    0.05       0  4999.9    0.05       0  5005.2    0.05       0
  5049.9    0.12       0  5163.6    0.05       0
Bank Sta=4999.9,5005.2
Exp/Cntr=0.3,0.1

Type RM Length L Ch R = 1,12942,426,426,426
BEGIN DESCRIPTION:
GRAPE CREEK 30.0
END DESCRIPTION:
XS GIS Cut Line= 3
      2798051.05     10184407.69      2797811.01     10184315.73
      2797249.45     10184262.84
#Sta/Elev= 30
  4649.1 1389.08  4740.5 1384.52  4751.2 1383.02  4794.1 1380.20  4812.9 1380.47
  4818.2 1378.96  4826.2 1378.39  4836.9 1373.70  4840.1 1373.13  4871.8 1371.14
  4931.6 1369.18  4941.6 1367.84  4961.7 1359.41  4971.8 1357.21  4992.1 1357.43
  4998.7 1356.09  4999.2 1355.59  5005.2 1356.09  5022.0 1357.59  5042.1 1357.36
  5052.1 1361.58  5072.2 1364.98  5090.6 1366.27  5132.7 1366.78  5182.7 1369.11
  5212.8 1372.64  5232.9 1376.33  5302.8 1381.06  5403.7 1392.65  5470.2 1398.11
#Mann=6,-1,0
  4649.1    0.05       0  4840.1    0.12       0  4871.8    0.05       0
  4998.7    0.05       0  5005.2    0.05       0  5132.7    0.12       0
Bank Sta=4998.7,5005.2
Exp/Cntr=0.3,0.1

Type RM Length L Ch R = 1,12516,800,800,800
BEGIN DESCRIPTION:
GRAPE CREEK 29.0
END DESCRIPTION:
XS GIS Cut Line= 3
      2798079.12     10183897.99      2797728.40     10183869.93
      2797276.22     10184007.19
#Sta/Elev= 30
  4546.6 1389.45  4570.1 1388.00  4610.2 1383.33  4697.6 1375.05  4796.3 1368.47
  4891.1 1365.46  4911.7 1364.42  4921.8 1362.99  4927.0 1363.51  4932.6 1360.38
  4959.9 1353.74  4984.9 1353.50  5013.0 1351.83  5013.5 1351.33  5019.5 1351.83
  5037.1 1358.80  5047.6 1360.98  5063.8 1362.94  5089.4 1363.45  5141.6 1367.52
  5162.5 1370.47  5200.6 1374.04  5205.8 1375.21  5236.1 1377.45  5271.6 1382.23
  5298.4 1387.34  5304.5 1389.36  5313.0 1389.95  5350.7 1396.30  5371.0 1398.40
#Mann=7,-1,0
  4546.6    0.12       0  4697.6    0.05       0  4796.3    0.12       0
  5013.0    0.07       0  5019.5    0.12       0  5236.1    0.05       0
  5313.0    0.12       0
Bank Sta=5013,5019.5
Exp/Cntr=0.3,0.1

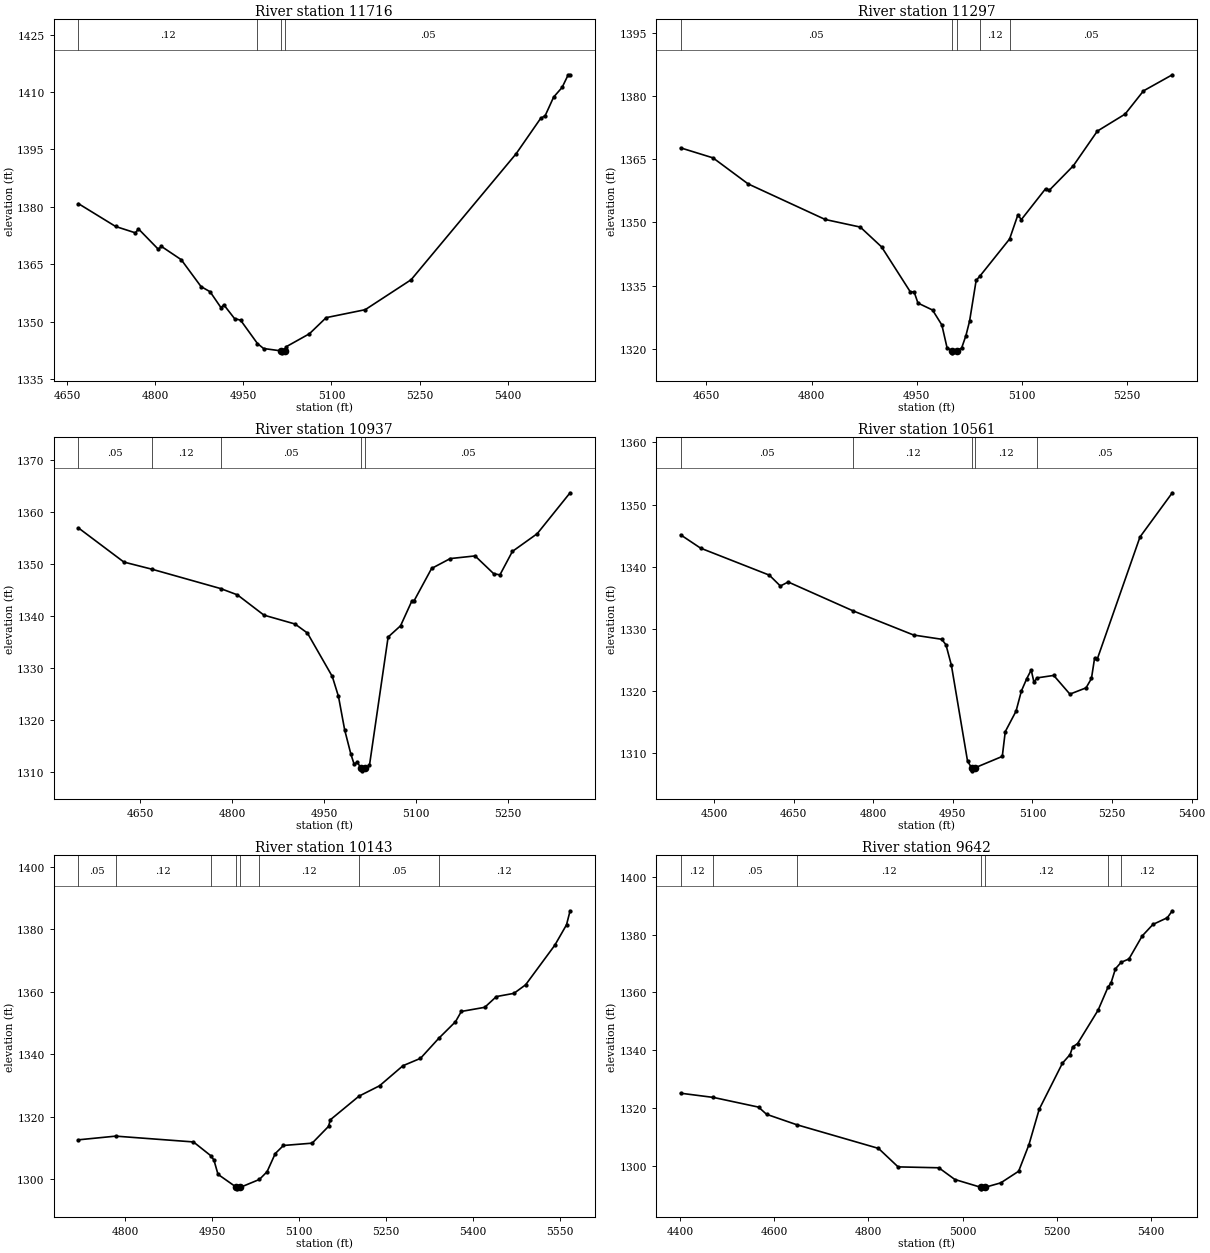
Type RM Length L Ch R = 1,11716,419,419,419
BEGIN DESCRIPTION:
GRAPE CREEK 27.0
END DESCRIPTION:
XS GIS Cut Line= 3
      2797641.10     10183090.57      2797190.74     10183219.54
      2796905.68     10183453.12
#Sta/Elev= 30
  4669.2 1380.82  4732.5 1374.86  4766.2 1373.19  4771.4 1374.22  4805.2 1368.90
  4810.4 1369.66  4844.2 1366.18  4877.9 1359.16  4893.3 1357.81  4911.7 1353.69
  4916.9 1354.36  4934.9 1350.81  4945.3 1350.37  4974.0 1344.27  4984.4 1342.98
  5014.7 1342.35  5015.2 1341.85  5021.5 1342.35  5023.4 1343.49  5062.4 1346.83
  5090.9 1351.04  5157.4 1353.12  5235.6 1360.95  5414.3 1393.85  5456.0 1403.08
  5463.8 1403.81  5478.2 1408.66  5492.6 1411.18  5503.0 1414.48  5506.2 1414.48
#Mann=4,-1,0
  4669.2    0.12       0  4974.0    0.05       0  5014.7    0.05       0
  5021.5    0.05       0
Bank Sta=5014.7,5021.5
Exp/Cntr=0.3,0.1

Type RM Length L Ch R = 1,11297,360,360,360
BEGIN DESCRIPTION:
GRAPE CREEK 26.0
END DESCRIPTION:
XS GIS Cut Line= 3
      2797581.89     10182752.33      2797305.68     10182753.11
      2796896.09     10182866.10
#Sta/Elev= 30
  4613.3 1367.69  4659.5 1365.31  4709.5 1359.14  4819.5 1350.69  4869.5 1348.89
  4899.9 1344.18  4941.0 1333.47  4946.2 1333.54  4951.7 1330.86  4972.5 1329.21
  4985.8 1325.66  4993.2 1320.26  5000.2 1319.55  5000.7 1319.05  5007.1 1319.55
  5014.0 1320.19  5020.1 1323.13  5025.3 1326.55  5034.7 1336.24  5040.6 1337.37
  5082.4 1346.07  5094.1 1351.73  5099.2 1350.68  5133.6 1357.97  5138.8 1357.59
  5173.2 1363.42  5207.5 1371.66  5247.1 1375.70  5273.3 1381.21  5314.4 1385.03
#Mann=5,-1,0
  4613.3    0.05       0  5000.2    0.05       0  5007.1    0.05       0
  5040.6    0.12       0  5082.4    0.05       0
Bank Sta=5000.2,5007.1
Exp/Cntr=0.3,0.1

Type RM Length L Ch R = 1,10937,376,376,376
BEGIN DESCRIPTION:
GRAPE CREEK 25.0
END DESCRIPTION:
XS GIS Cut Line= 3
      2797614.66     10182499.82      2797073.74     10182412.53
      2796822.76     10182454.62
#Sta/Elev= 30
  4549.2 1356.88  4623.4 1350.33  4669.5 1348.95  4781.2 1345.25  4808.7 1344.04
  4852.0 1340.15  4902.7 1338.45  4922.9 1336.72  4963.5 1328.39  4973.6 1324.55
  4983.7 1318.14  4993.9 1313.46  4999.1 1311.58  5004.2 1311.92  5010.7 1310.79
  5011.2 1310.29  5017.6 1310.79  5024.2 1311.37  5054.6 1335.95  5074.9 1338.11
  5093.6 1342.93  5097.1 1342.93  5125.6 1349.11  5156.0 1351.00  5196.5 1351.51
  5227.0 1348.09  5237.1 1347.88  5257.4 1352.37  5297.9 1355.77  5351.6 1363.62
#Mann=5,-1,0
  4549.2    0.05       0  4669.5    0.12       0  4781.2    0.05       0
  5010.7    0.05       0  5017.6    0.05       0
Bank Sta=5010.7,5017.6
Exp/Cntr=0.3,0.1

Type RM Length L Ch R = 1,10561,418,418,418
BEGIN DESCRIPTION:
GRAPE CREEK 24.0
END DESCRIPTION:
XS GIS Cut Line= 3
      2797742.44     10182339.28      2797404.19     10182089.87
      2796905.64     10182003.10
#Sta/Elev= 30
  4437.1 1345.13  4474.7 1342.99  4604.2 1338.65  4625.0 1336.90  4639.7 1337.55
  4762.7 1332.88  4876.1 1329.02  4929.0 1328.34  4937.0 1327.45  4947.2 1324.17
  4977.6 1308.77  4985.1 1307.69  4985.6 1307.19  4992.0 1307.69  5043.1 1309.51
  5048.7 1313.49  5069.0 1316.78  5079.1 1320.03  5089.3 1322.03  5097.6 1323.41
  5102.7 1321.45  5108.6 1322.13  5140.0 1322.53  5170.5 1319.52  5200.9 1320.53
  5211.1 1322.04  5216.9 1325.25  5221.9 1325.12  5302.5 1344.78  5363.4 1351.89
#Mann=5,-1,0
  4437.1    0.05       0  4762.7    0.12       0  4985.1    0.07       0
  4992.0    0.12       0  5108.6    0.05       0
Bank Sta=4985.1,4992
Exp/Cntr=0.3,0.1

Type RM Length L Ch R = 1,10143,501,501,501
BEGIN DESCRIPTION:
GRAPE CREEK 23.0
END DESCRIPTION:
XS GIS Cut Line= 3
      2797383.94     10181500.66      2797078.41     10181812.42
      2796669.53     10181866.84
#Sta/Elev= 30
  4719.2 1312.61  4783.6 1313.79  4917.8 1311.93  4947.3 1307.59  4953.1 1306.17
  4960.2 1301.56  4992.0 1297.42  4992.5 1296.92  4999.0 1297.42  5031.6 1299.92
  5044.9 1302.39  5059.1 1308.22  5073.2 1310.80  5122.8 1311.54  5151.1 1316.92
  5154.1 1319.01  5203.7 1326.59  5239.2 1329.91  5279.6 1336.33  5309.8 1338.68
  5341.2 1345.06  5370.3 1350.41  5380.4 1353.70  5420.8 1355.02  5440.9 1358.46
  5471.2 1359.49  5491.4 1362.23  5541.8 1374.90  5562.0 1381.43  5568.2 1385.92
#Mann=8,-1,0
  4719.2    0.05       0  4783.6    0.12       0  4947.3    0.05       0
  4992.0    0.05       0  4999.0    0.05       0  5031.6    0.12       0
  5203.7    0.05       0  5341.2    0.12       0
Bank Sta=4992,4999
Exp/Cntr=0.3,0.1

Type RM Length L Ch R = 1,9642,529,529,529
BEGIN DESCRIPTION:
GRAPE CREEK 22.0
END DESCRIPTION:
XS GIS Cut Line= 3
      2797393.25     10181209.20      2796920.98     10181324.54
      2796429.51     10181592.05
#Sta/Elev= 30
  4400.5 1325.12  4470.3 1323.66  4566.2 1320.31  4583.3 1317.82  4647.3 1314.22
  4821.3 1306.02  4863.0 1299.62  4949.6 1299.31  4983.8 1295.25  5039.7 1292.52
  5040.2 1292.02  5047.3 1292.52  5081.4 1294.09  5119.4 1298.11  5141.3 1307.31
  5163.1 1319.55  5212.5 1335.50  5228.7 1338.49  5234.4 1341.16  5244.8 1342.31
  5288.5 1353.90  5309.2 1361.74  5316.0 1363.35  5325.3 1368.20  5337.4 1370.43
  5354.0 1371.59  5382.2 1379.56  5405.0 1383.54  5435.7 1385.87  5446.2 1388.27
#Mann=7,-1,0
  4400.5    0.12       0  4470.3    0.05       0  4647.3    0.12       0
  5039.7    0.07       0  5047.3    0.12       0  5309.2    0.05       0
  5337.4    0.12       0
Bank Sta=5039.7,5047.3
Exp/Cntr=0.3,0.1

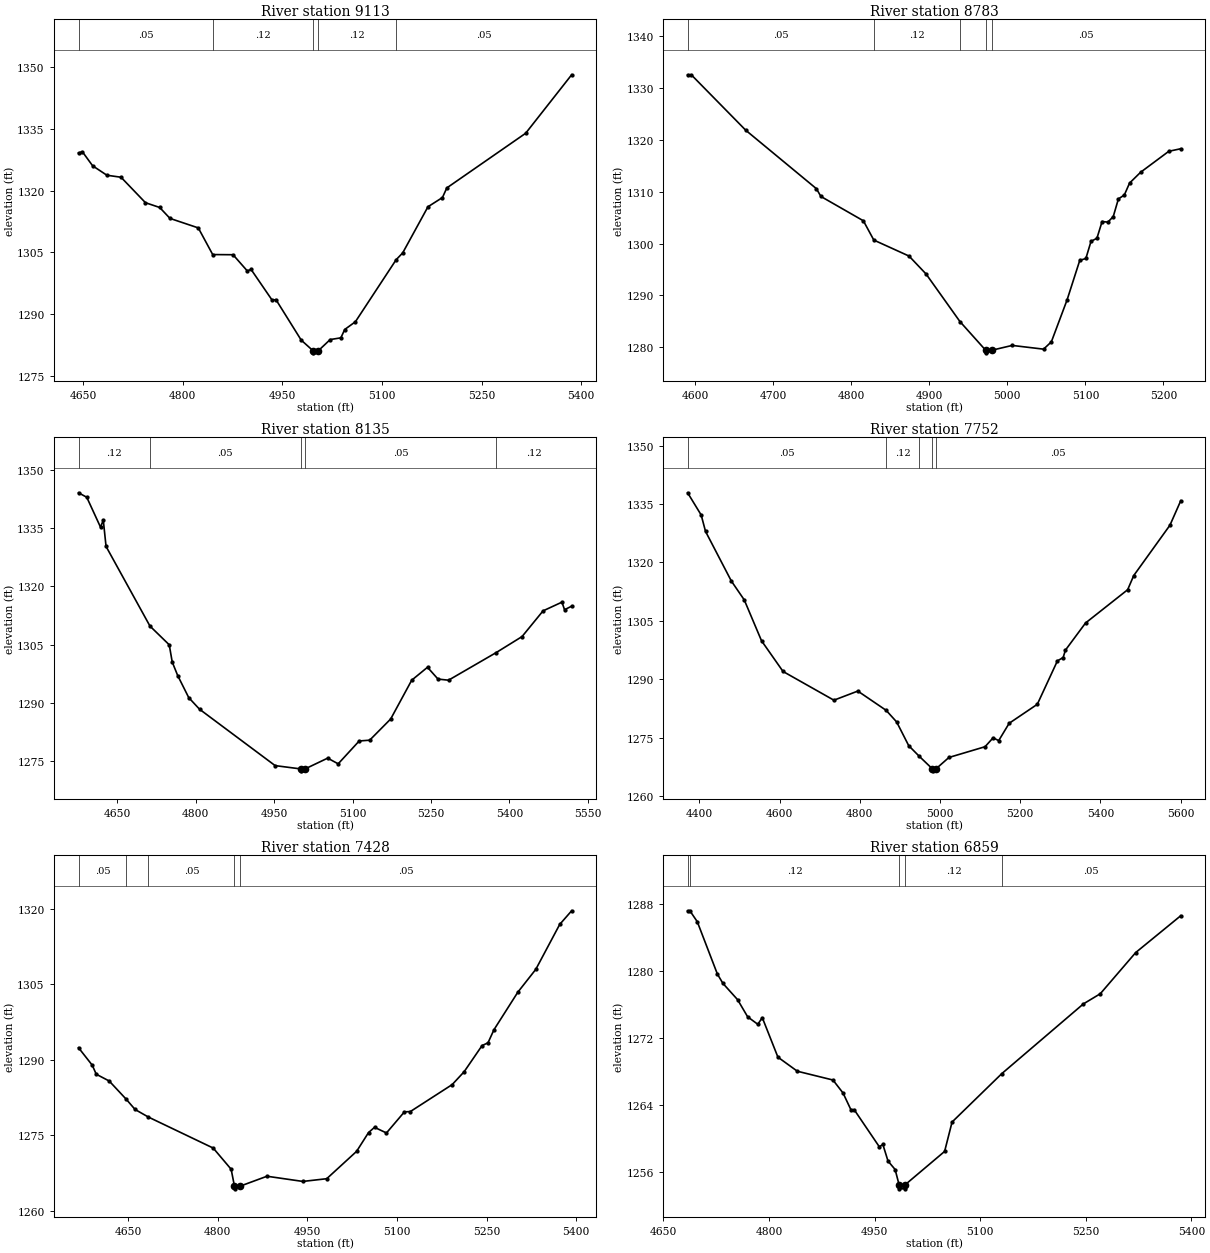
Type RM Length L Ch R = 1,9113,330,330,330
BEGIN DESCRIPTION:
GRAPE CREEK 21.0
END DESCRIPTION:
XS GIS Cut Line= 3
      2796896.08     10180735.32      2796662.23     10180877.19
      2796250.69     10181101.67
#Sta/Elev= 30
  4643.3 1329.16  4649.1 1329.47  4664.6 1326.04  4686.0 1323.75  4707.3 1323.26
  4744.1 1317.06  4765.5 1315.90  4781.0 1313.24  4823.6 1310.93  4845.3 1304.44
  4875.9 1304.40  4897.3 1300.47  4903.1 1300.81  4934.8 1293.33  4940.5 1293.47
  4978.5 1283.62  4996.4 1281.02  4996.9 1280.52  5004.2 1281.02  5022.1 1283.75
  5038.2 1284.17  5044.0 1286.20  5060.1 1288.09  5121.4 1303.18  5131.3 1304.85
  5169.3 1316.07  5191.1 1318.32  5197.7 1320.66  5316.4 1333.97  5385.6 1348.20
#Mann=5,-1,0
  4643.3    0.05       0  4845.3    0.12       0  4996.4    0.07       0
  5004.2    0.12       0  5121.4    0.05       0
Bank Sta=4996.4,5004.2
Exp/Cntr=0.3,0.1

Type RM Length L Ch R = 1,8783,648,648,648
BEGIN DESCRIPTION:
GRAPE CREEK 20.0
END DESCRIPTION:
XS GIS Cut Line= 3
      2796910.04     10180573.24      2796408.16     10180616.88
      2796324.01     10180713.51
#Sta/Elev= 30
  4590.3 1332.54  4595.0 1332.54  4664.9 1321.83  4755.3 1310.58  4761.1 1309.08
  4815.5 1304.39  4828.9 1300.67  4874.0 1297.59  4895.8 1294.14  4939.2 1284.97
  4972.2 1279.43  4972.7 1278.93  4980.0 1279.43  5006.2 1280.36  5046.4 1279.64
  5056.4 1281.05  5076.5 1289.12  5092.8 1296.76  5100.6 1297.12  5107.2 1300.42
  5114.8 1301.03  5121.4 1304.25  5128.8 1304.13  5135.7 1305.20  5142.3 1308.61
  5149.9 1309.36  5156.6 1311.66  5170.8 1313.75  5206.9 1317.79  5222.2 1318.28
#Mann=5,-1,0
  4590.3    0.05       0  4828.9    0.12       0  4939.2    0.05       0
  4972.2    0.05       0  4980.0    0.05       0
Bank Sta=4972.2,4980
Exp/Cntr=0.3,0.1

Type RM Length L Ch R = 1,8135,383,383,383
BEGIN DESCRIPTION:
GRAPE CREEK 19.0
END DESCRIPTION:
XS GIS Cut Line= 3
      2796855.70     10180053.12      2796565.59     10179955.99
      2795931.24     10180019.89
#Sta/Elev= 30
  4575.6 1344.20  4591.4 1343.04  4617.7 1335.32  4623.0 1337.14  4628.3 1330.34
  4712.3 1309.77  4749.2 1304.93  4754.9 1300.49  4765.4 1296.98  4786.5 1291.29
  4807.1 1288.30  4951.8 1273.73  5000.5 1272.88  5001.0 1272.38  5009.1 1272.88
  5052.3 1275.66  5072.4 1274.19  5112.6 1280.09  5132.7 1280.30  5172.9 1285.78
  5213.1 1295.79  5243.3 1299.13  5263.4 1296.08  5283.5 1295.79  5374.8 1302.93
  5424.2 1307.06  5464.4 1313.70  5500.5 1315.95  5505.5 1314.00  5519.1 1314.91
#Mann=5,-1,0
  4575.6    0.12       0  4712.3    0.05       0  5000.5    0.05       0
  5009.1    0.05       0  5374.8    0.12       0
Bank Sta=5000.5,5009.1
Exp/Cntr=0.3,0.1

Type RM Length L Ch R = 1,7752,324,324,324
BEGIN DESCRIPTION:
GRAPE CREEK 18.0
END DESCRIPTION:
XS GIS Cut Line= 3
      2796977.13     10179742.46      2796579.62     10179586.57
      2795778.75     10179636.33
#Sta/Elev= 30
  4370.7 1337.88  4404.5 1332.18  4415.3 1327.98  4479.7 1315.23  4511.9 1310.39
  4554.9 1299.91  4608.6 1292.02  4735.4 1284.65  4795.0 1286.99  4865.6 1282.05
  4891.8 1279.07  4921.9 1272.98  4947.9 1270.28  4981.0 1267.02  4981.5 1266.52
  4989.7 1267.02  5022.1 1269.95  5112.2 1272.71  5132.3 1275.00  5146.2 1274.27
  5172.3 1278.72  5242.5 1283.60  5292.6 1294.74  5306.9 1295.60  5312.6 1297.50
  5362.7 1304.46  5467.7 1313.00  5482.9 1316.64  5573.1 1329.55  5600.1 1335.84
#Mann=5,-1,0
  4370.7    0.05       0  4865.6    0.12       0  4947.9    0.05       0
  4981.0    0.05       0  4989.7    0.05       0
Bank Sta=4981,4989.7
Exp/Cntr=0.3,0.1

Type RM Length L Ch R = 1,7428,569,569,569
BEGIN DESCRIPTION:
GRAPE CREEK 17.0
END DESCRIPTION:
XS GIS Cut Line= 3
      2796655.72     10179403.13      2796482.98     10179306.00
      2795855.66     10179303.11
#Sta/Elev= 30
  4567.0 1292.39  4590.0 1288.92  4596.7 1287.13  4618.4 1285.78  4646.9 1282.16
  4661.7 1280.13  4684.1 1278.62  4792.5 1272.47  4822.5 1268.27  4828.1 1264.88
  4828.6 1264.38  4836.8 1264.88  4882.5 1266.88  4942.5 1265.85  4982.5 1266.39
  5032.5 1271.82  5052.5 1275.55  5062.5 1276.59  5082.5 1275.47  5112.5 1279.65
  5122.5 1279.72  5192.5 1285.07  5212.5 1287.62  5242.5 1292.81  5252.5 1293.37
  5262.5 1295.97  5302.5 1303.43  5332.5 1307.95  5372.5 1316.86  5392.5 1319.57
#Mann=5,-1,0
  4567.0    0.05       0  4646.9    0.12       0  4684.1    0.05       0
  4828.1    0.05       0  4836.8    0.05       0
Bank Sta=4828.1,4836.8
Exp/Cntr=0.3,0.1

Type RM Length L Ch R = 1,6859,445,445,445
BEGIN DESCRIPTION:
GRAPE CREEK 16.0
END DESCRIPTION:
XS GIS Cut Line= 3
      2796705.69     10179153.12      2796554.68     10178970.88
      2796506.36     10178509.48
#Sta/Elev= 30
  4684.4 1287.20  4687.6 1287.20  4698.1 1285.90  4726.7 1279.64  4734.6 1278.52
  4755.4 1276.58  4769.7 1274.53  4784.1 1273.64  4790.5 1274.43  4812.7 1269.71
  4840.3 1268.03  4890.9 1266.98  4905.2 1265.43  4916.4 1263.43  4921.1 1263.43
  4956.7 1259.01  4961.8 1259.28  4969.1 1257.30  4979.2 1256.29  4984.8 1254.48
  4985.3 1253.98  4993.1 1253.98  4993.6 1254.48  5049.5 1258.45  5060.1 1261.96
  5130.7 1267.74  5246.6 1276.07  5270.7 1277.29  5321.0 1282.21  5385.0 1286.61
#Mann=5,-1,0
  4684.4    0.05       0  4687.6    0.12       0  4984.8    0.07       0
  4993.6    0.12       0  5130.7    0.05       0
Bank Sta=4984.8,4993.6
Exp/Cntr=0.3,0.1