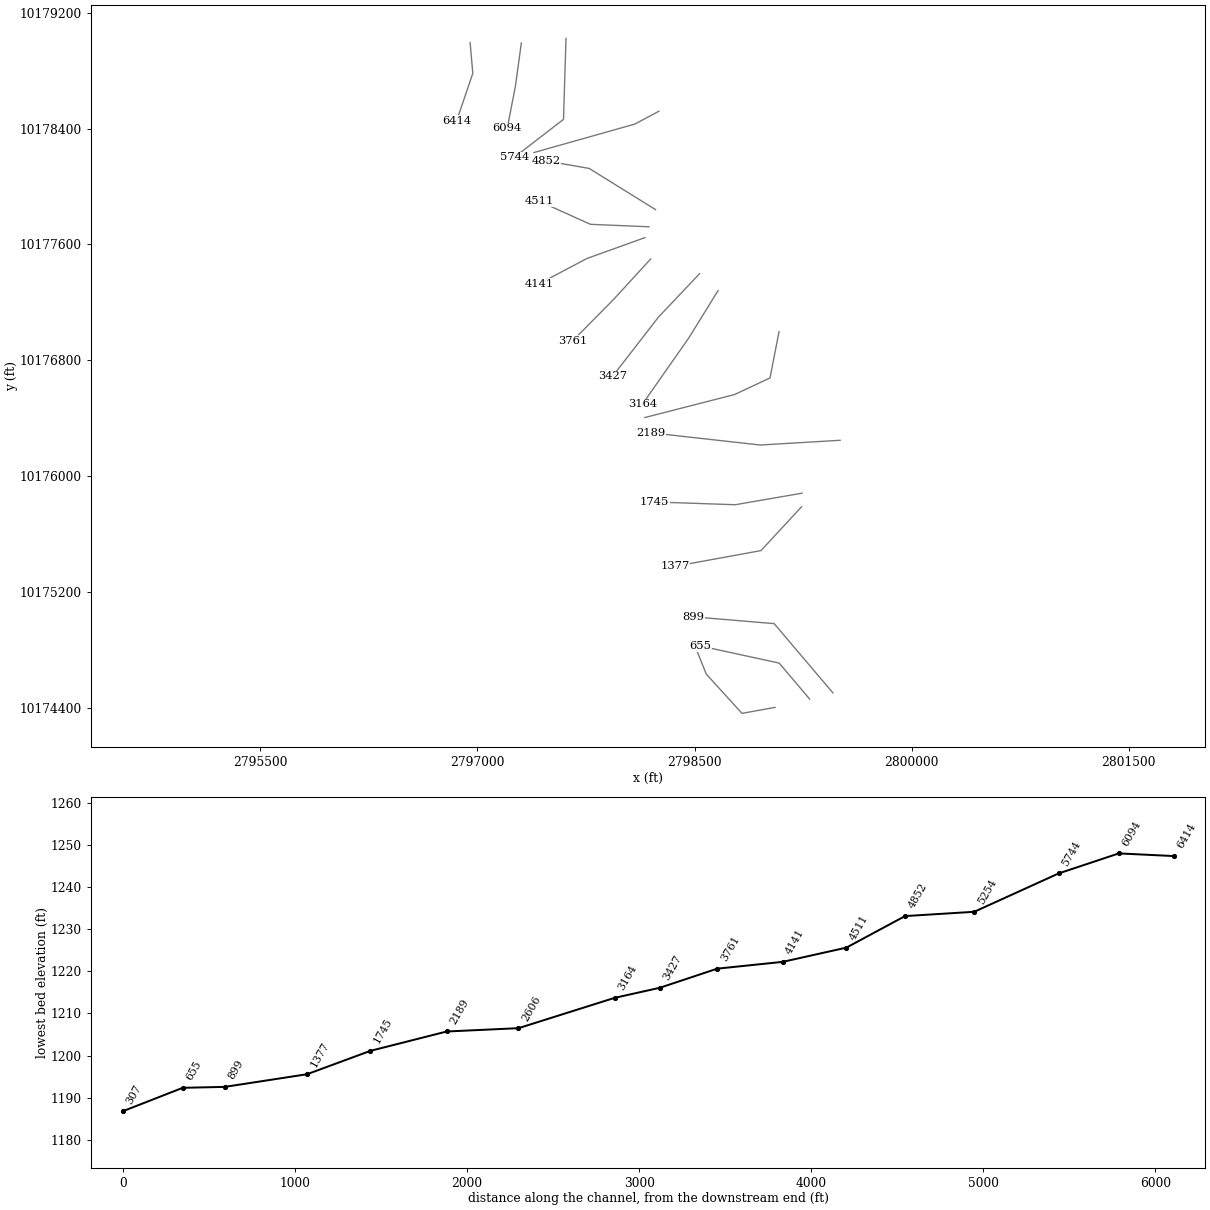
HEC-RAS study GRAPE CREEK.prj: GRAPE CREEK Base Level Engineering

--- GRAPE CREEK.g01 (geometry) --- (continued)

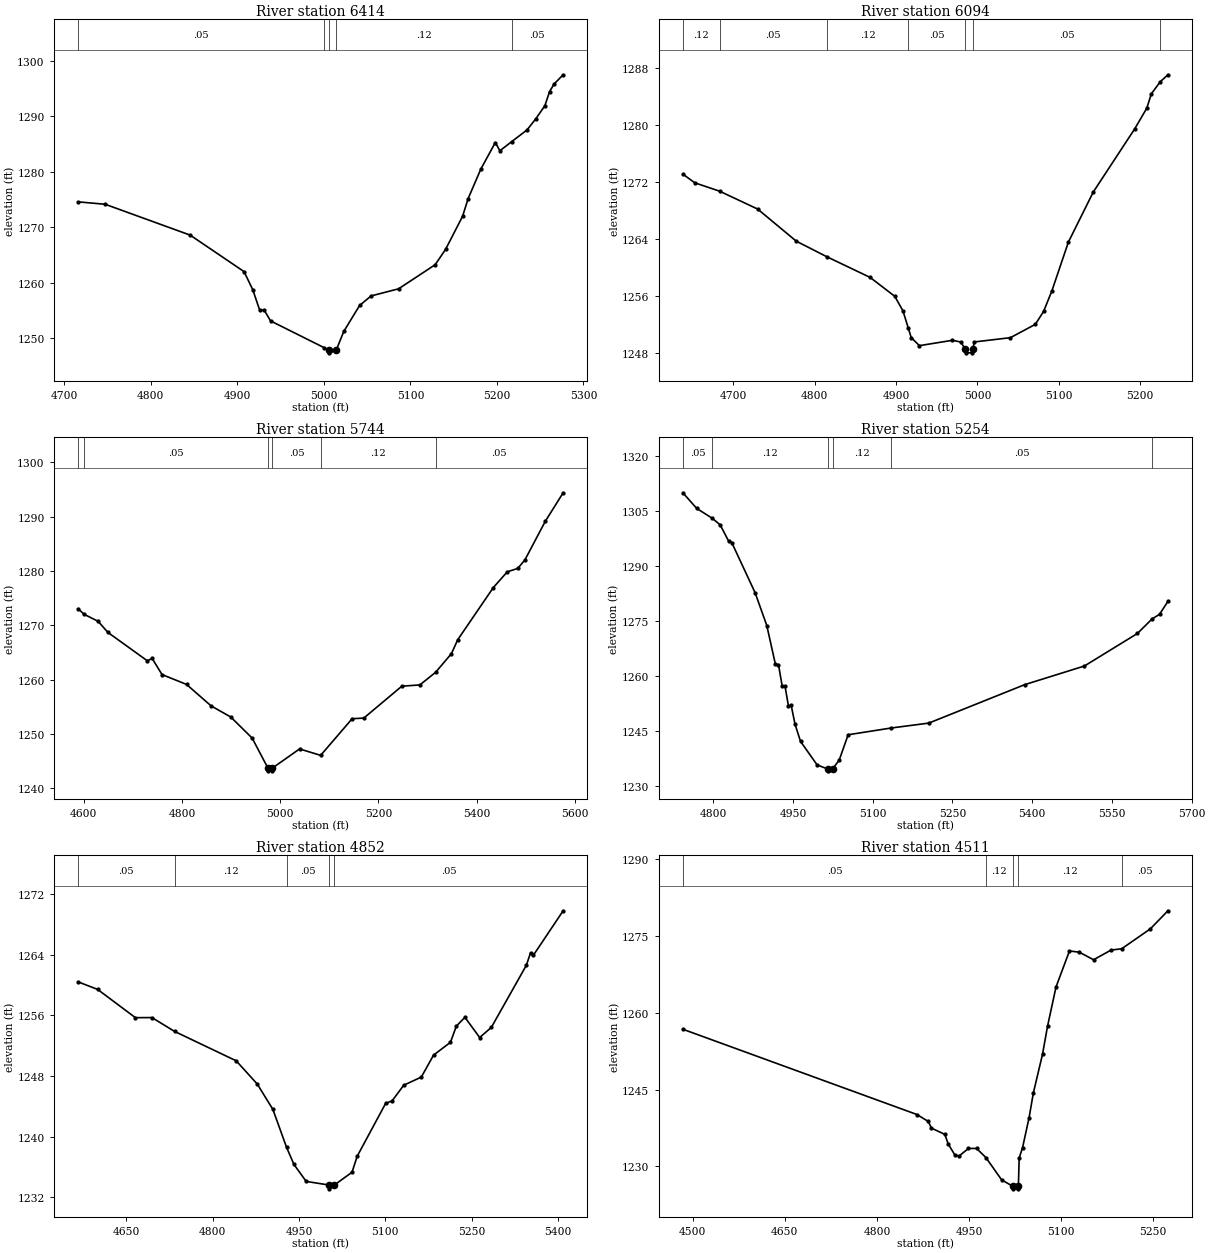
Type RM Length L Ch R = 1,6414,320,320,320
BEGIN DESCRIPTION:
GRAPE CREEK 15.0
END DESCRIPTION:
XS GIS Cut Line= 3
      2796949.04     10178994.22      2796967.74     10178782.27
      2796855.68     10178453.09
#Sta/Elev= 30
  4716.0 1274.59  4747.2 1274.16  4845.5 1268.59  4907.8 1262.00  4917.9 1258.71
  4925.8 1255.07  4931.0 1255.07  4938.4 1253.11  5000.2 1248.29  5005.5 1247.85
  5006.0 1247.35  5014.3 1247.85  5023.0 1251.21  5041.3 1255.90  5054.6 1257.62
  5086.3 1258.90  5128.6 1263.25  5140.6 1266.01  5160.3 1271.99  5166.7 1275.18
  5181.4 1280.51  5198.1 1285.30  5203.4 1283.81  5216.9 1285.44  5234.7 1287.56
  5244.8 1289.56  5255.4 1291.94  5260.8 1294.48  5266.1 1295.87  5276.5 1297.52
#Mann=5,-1,0
  4716.0    0.05       0  5000.2    0.12       0  5005.5    0.05       0
  5014.3    0.12       0  5216.9    0.05       0
Bank Sta=5005.5,5014.3
Exp/Cntr=0.3,0.1

Type RM Length L Ch R = 1,6094,350,350,350
BEGIN DESCRIPTION:
GRAPE CREEK 14.0
END DESCRIPTION:
XS GIS Cut Line= 3
      2797302.88     10178991.19      2797262.34     10178694.98
      2797205.68     10178403.10
#Sta/Elev= 30
  4637.9 1273.07  4652.6 1271.85  4683.0 1270.68  4729.8 1268.17  4777.3 1263.66
  4815.1 1261.46  4868.1 1258.57  4898.4 1255.92  4908.5 1253.87  4914.9 1251.50
  4918.6 1250.13  4928.7 1248.99  4969.3 1249.74  4979.5 1249.50  4985.3 1248.48
  4985.8 1247.98  4993.6 1247.98  4994.1 1248.48  4996.4 1249.51  5040.6 1250.11
  5071.2 1251.98  5081.4 1253.80  5091.6 1256.69  5111.9 1263.54  5142.5 1270.57
  5193.4 1279.43  5208.3 1282.34  5213.8 1284.34  5224.8 1286.04  5234.2 1287.02
#Mann=7,-1,0
  4637.9    0.12       0  4683.0    0.05       0  4815.1    0.12       0
  4914.9    0.05       0  4985.3    0.07       0  4994.1    0.05       0
  5224.8    0.05       0
Bank Sta=4985.3,4994.1
Exp/Cntr=0.3,0.1

Type RM Length L Ch R = 1,5744,490,490,490
BEGIN DESCRIPTION:
GRAPE CREEK 13.0
END DESCRIPTION:
XS GIS Cut Line= 3
      2797611.49     10179023.83      2797594.35     10178464.29
      2797255.67     10178203.10
#Sta/Elev= 30
  4588.7 1273.04  4601.3 1272.01  4629.4 1270.74  4649.4 1268.69  4729.5 1263.48
  4739.5 1263.90  4759.5 1260.94  4809.5 1259.12  4859.5 1255.17  4899.6 1253.12
  4943.1 1249.24  4975.2 1243.72  4975.7 1243.22  4983.6 1243.22  4984.1 1243.72
  5039.6 1247.25  5082.5 1246.07  5146.6 1252.81  5170.4 1252.93  5247.8 1258.80
  5284.5 1259.03  5316.5 1261.35  5348.8 1264.79  5361.5 1267.34  5434.0 1276.94
  5462.5 1279.85  5483.8 1280.47  5498.3 1282.03  5539.9 1289.15  5576.2 1294.39
#Mann=6,-1,0
  4588.7    0.12       0  4601.3    0.05       0  4975.2    0.05       0
  4984.1    0.05       0  5082.5    0.12       0  5316.5    0.05       0
Bank Sta=4975.2,4984.1
Exp/Cntr=0.3,0.1

Type RM Length L Ch R = 1,5254,402,402,402
BEGIN DESCRIPTION:
GRAPE CREEK 12.0
END DESCRIPTION:
XS GIS Cut Line= 3
      2798253.72     10178520.42      2798086.90     10178431.56
      2797390.45     10178235.24
#Sta/Elev= 30
  4742.7 1310.01  4768.8 1305.74  4797.8 1303.07  4812.8 1301.27  4829.1 1296.74
  4834.7 1296.42  4878.7 1282.71  4900.6 1273.78  4916.9 1263.15  4922.6 1263.11
  4929.6 1257.23  4934.9 1257.23  4941.3 1251.86  4946.5 1251.98  4953.8 1246.82
  4964.1 1242.15  4995.3 1235.74  5015.2 1234.62  5015.7 1234.12  5024.3 1234.62
  5036.9 1237.07  5053.7 1243.97  5135.1 1245.82  5205.4 1247.15  5385.8 1257.64
  5498.2 1262.73  5597.9 1271.61  5625.6 1275.59  5639.5 1276.83  5655.3 1280.35
#Mann=6,-1,0
  4742.7    0.05       0  4797.8    0.12       0  5015.2    0.07       0
  5024.3    0.12       0  5135.1    0.05       0  5625.6    0.12       0
Bank Sta=5015.2,5024.3
Exp/Cntr=0.3,0.1

Type RM Length L Ch R = 1,4852,341,341,341
BEGIN DESCRIPTION:
GRAPE CREEK 11.0
END DESCRIPTION:
XS GIS Cut Line= 3
      2798230.32     10177840.80      2797771.42     10178125.45
      2797472.73     10178177.49
#Sta/Elev= 30
  4565.9 1260.40  4599.8 1259.41  4665.5 1255.68  4694.3 1255.69  4733.5 1253.87
  4840.7 1249.99  4877.3 1246.93  4904.5 1243.58  4928.2 1238.59  4941.1 1236.32
  4962.4 1234.08  5002.2 1233.60  5002.7 1233.10  5011.3 1233.60  5042.1 1235.29
  5051.0 1237.39  5100.5 1244.37  5111.7 1244.70  5132.0 1246.77  5162.5 1247.84
  5183.8 1250.74  5213.2 1252.43  5223.4 1254.56  5238.3 1255.73  5264.0 1253.06
  5284.3 1254.40  5345.2 1262.60  5352.4 1264.25  5357.4 1263.92  5409.1 1269.78
#Mann=5,-1,0
  4565.9    0.05       0  4733.5    0.12       0  4928.2    0.05       0
  5002.2    0.03       0  5011.3    0.05       0
Bank Sta=5002.2,5011.3
Exp/Cntr=0.3,0.1

Type RM Length L Ch R = 1,4511,370,370,370
BEGIN DESCRIPTION:
GRAPE CREEK 10.0
END DESCRIPTION:
XS GIS Cut Line= 3
      2798185.06     10177722.34      2797780.48     10177739.25
      2797429.57     10177897.57
#Sta/Elev= 30
  4484.0 1256.77  4865.2 1240.12  4883.7 1238.76  4888.8 1237.47  4910.6 1236.24
  4916.1 1234.37  4927.1 1232.19  4933.7 1232.01  4949.0 1233.49  4962.3 1233.50
  4977.6 1231.70  5003.1 1227.37  5021.2 1226.11  5021.7 1225.61  5029.9 1225.61
  5030.4 1226.11  5031.7 1231.63  5037.2 1233.66  5047.8 1239.49  5054.8 1244.34
  5069.7 1251.89  5077.9 1257.38  5091.7 1265.03  5113.6 1272.06  5129.7 1271.81
  5152.8 1270.34  5181.4 1272.23  5198.6 1272.48  5245.3 1276.37  5273.9 1279.90
#Mann=5,-1,0
  4484.0    0.05       0  4977.6    0.12       0  5021.2    0.07       0
  5030.4    0.12       0  5198.6    0.05       0
Bank Sta=5021.2,5030.4
Exp/Cntr=0.3,0.1

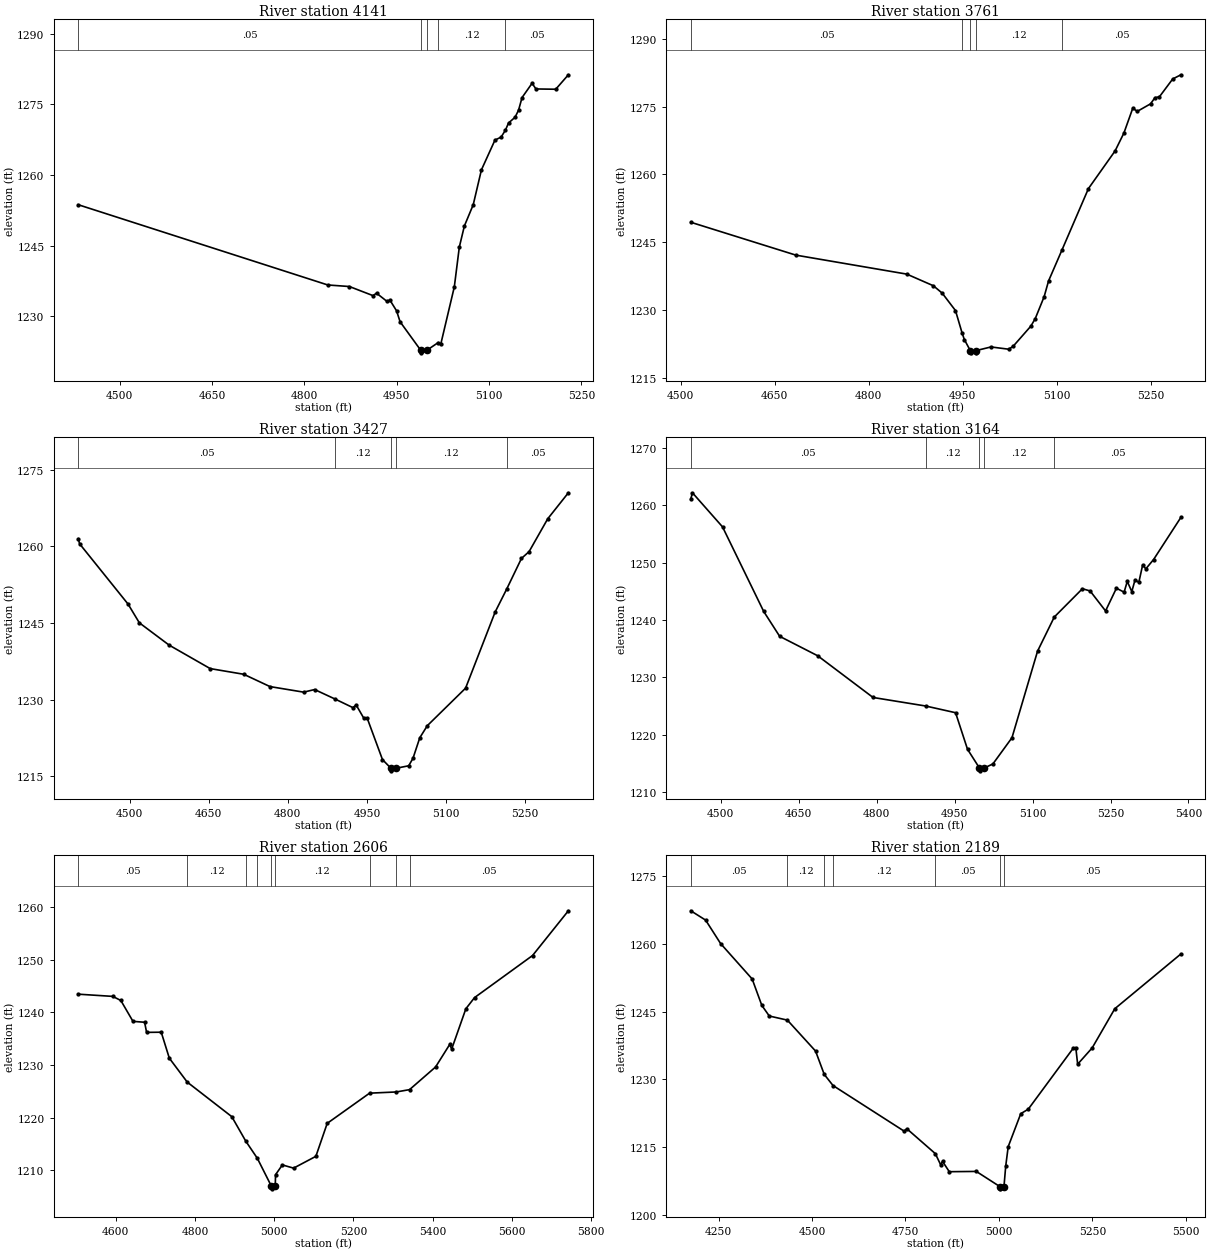
Type RM Length L Ch R = 1,4141,380,380,380
BEGIN DESCRIPTION:
GRAPE CREEK 9.0
END DESCRIPTION:
XS GIS Cut Line= 3
      2798157.04     10177647.52      2797755.68     10177503.11
      2797429.10     10177330.36
#Sta/Elev= 30
  4432.9 1253.68  4838.2 1236.64  4873.3 1236.31  4911.6 1234.38  4917.3 1234.90
  4933.6 1233.23  4939.3 1233.38  4949.9 1231.15  4955.6 1228.83  4989.4 1222.73
  4989.9 1222.23  4998.6 1222.73  5017.6 1224.42  5021.7 1224.08  5043.7 1236.25
  5051.8 1244.68  5060.0 1249.16  5074.4 1253.68  5087.7 1261.08  5109.7 1267.41
  5119.6 1268.03  5126.7 1269.51  5131.7 1271.03  5142.3 1272.25  5148.0 1273.75
  5153.7 1276.44  5170.0 1279.47  5176.2 1278.26  5208.4 1278.20  5228.9 1281.27
#Mann=5,-1,0
  4432.9    0.05       0  4989.4    0.05       0  4998.6    0.05       0
  5017.6    0.12       0  5126.7    0.05       0
Bank Sta=4989.4,4998.6
Exp/Cntr=0.3,0.1

Type RM Length L Ch R = 1,3761,334,334,334
BEGIN DESCRIPTION:
GRAPE CREEK 8.0
END DESCRIPTION:
XS GIS Cut Line= 3
      2798196.04     10177499.47      2797938.83     10177218.87
      2797656.66     10176933.59
#Sta/Elev= 30
  4516.1 1249.45  4683.8 1242.19  4860.7 1238.00  4903.1 1235.43  4917.2 1233.80
  4938.4 1229.95  4948.8 1225.06  4952.5 1223.56  4962.0 1221.12  4962.5 1220.62
  4970.8 1220.62  4971.3 1221.12  4995.0 1221.92  5023.3 1221.42  5030.4 1222.07
  5058.6 1226.51  5065.7 1228.20  5079.8 1233.01  5086.9 1236.51  5108.3 1243.34
  5150.5 1256.89  5193.0 1265.20  5207.1 1269.16  5221.2 1274.63  5228.4 1273.93
  5249.5 1275.59  5256.6 1276.95  5263.7 1277.15  5284.9 1281.08  5298.0 1282.01
#Mann=5,-1,0
  4516.1    0.05       0  4948.8    0.12       0  4962.0    0.07       0
  4971.3    0.12       0  5108.3    0.05       0
Bank Sta=4962,4971.3
Exp/Cntr=0.3,0.1

Type RM Length L Ch R = 1,3427,263,263,263
BEGIN DESCRIPTION:
GRAPE CREEK 7.0
END DESCRIPTION:
XS GIS Cut Line= 3
      2798534.22     10177398.09      2798250.57     10177098.85
      2797934.17     10176690.50
#Sta/Elev= 30
  4402.7 1261.51  4405.3 1260.51  4497.1 1248.72  4518.5 1245.05  4574.9 1240.69
  4652.8 1236.09  4716.3 1234.98  4766.1 1232.57  4829.9 1231.48  4850.7 1231.99
  4889.7 1230.12  4923.1 1228.46  4929.5 1228.96  4944.0 1226.36  4950.3 1226.40
  4979.3 1218.28  4995.4 1216.58  4995.9 1216.08  5004.7 1216.58  5029.0 1217.07
  5037.2 1218.55  5050.0 1222.55  5064.3 1224.92  5136.8 1232.26  5192.9 1247.18
  5214.7 1251.65  5242.7 1257.65  5257.2 1258.99  5292.5 1265.41  5331.6 1270.50
#Mann=5,-1,0
  4402.7    0.05       0  4889.7    0.12       0  4995.4    0.07       0
  5004.7    0.12       0  5214.7    0.05       0
Bank Sta=4995.4,5004.7
Exp/Cntr=0.3,0.1

Type RM Length L Ch R = 1,3164,558,558,558
BEGIN DESCRIPTION:
GRAPE CREEK 6.0
END DESCRIPTION:
XS GIS Cut Line= 3
      2798662.09     10177281.26      2798459.44     10176953.89
      2798139.19     10176496.84
#Sta/Elev= 30
  4442.3 1261.11  4445.5 1262.19  4503.4 1256.24  4582.6 1241.49  4613.3 1237.15
  4686.6 1233.75  4793.0 1226.48  4894.3 1224.99  4951.8 1223.82  4974.8 1217.44
  4997.7 1214.18  4998.2 1213.68  5007.0 1214.18  5023.6 1214.88  5060.3 1219.45
  5109.6 1234.57  5141.8 1240.52  5195.9 1245.45  5210.7 1245.06  5240.4 1241.58
  5261.3 1245.54  5276.1 1244.85  5282.2 1246.73  5290.9 1244.95  5297.0 1246.95
  5304.5 1246.58  5311.8 1249.61  5317.9 1248.92  5332.8 1250.54  5385.4 1257.90
#Mann=5,-1,0
  4442.3    0.05       0  4894.3    0.12       0  4997.7    0.07       0
  5007.0    0.12       0  5141.8    0.05       0
Bank Sta=4997.7,5007
Exp/Cntr=0.3,0.1

Type RM Length L Ch R = 1,2606,417,417,417
BEGIN DESCRIPTION:
Mapping XS 9b6780d8
END DESCRIPTION:
XS GIS Cut Line= 4
      2799083.48     10176998.63      2799020.98     10176678.32
      2798776.18     10176563.73      2798156.36     10176404.87
#Sta/Elev= 30
  4505.7 1243.44  4592.8 1243.02  4613.2 1242.24  4643.8 1238.28  4673.1 1238.11
  4678.2 1236.19  4715.1 1236.22  4735.5 1231.29  4780.7 1226.75  4893.1 1220.19
  4928.4 1215.54  4957.5 1212.29  4993.0 1206.99  4993.5 1206.49  5002.7 1206.99
  5003.5 1209.18  5020.7 1211.03  5049.0 1210.42  5105.2 1212.66  5133.8 1218.92
  5240.7 1224.65  5308.2 1224.88  5341.5 1225.32  5407.2 1229.62  5442.8 1233.89
  5447.9 1233.04  5483.6 1240.67  5505.5 1242.79  5651.9 1250.78  5742.2 1259.27
#Mann=9,-1,0
  4505.7    0.05       0  4780.7    0.12       0  4928.4    0.05       0
  4957.5    0.12       0  4993.0    0.07       0  5002.7    0.12       0
  5240.7    0.05       0  5308.2    0.12       0  5341.5    0.05       0
Bank Sta=4993,5002.7
Exp/Cntr=0.3,0.1

Type RM Length L Ch R = 1,2189,444,444,444
BEGIN DESCRIPTION:
GRAPE CREEK 5.0
END DESCRIPTION:
XS GIS Cut Line= 3
      2799505.33     10176247.79      2798953.55     10176215.06
      2798199.88     10176299.15
#Sta/Elev= 30
  4175.7 1267.34  4215.4 1265.27  4255.5 1260.07  4339.9 1252.22  4365.7 1246.37
  4385.7 1244.01  4434.1 1243.10  4509.5 1236.24  4532.7 1231.07  4556.2 1228.60
  4746.4 1218.49  4753.7 1219.02  4829.9 1213.50  4844.1 1211.04  4849.1 1211.79
  4867.2 1209.50  4939.5 1209.56  5002.5 1206.20  5003.0 1205.70  5013.5 1206.20
  5018.1 1210.69  5024.8 1215.05  5058.4 1222.36  5078.5 1223.36  5199.2 1236.92
  5205.6 1237.01  5210.6 1233.33  5249.5 1236.95  5309.9 1245.62  5486.8 1257.77
#Mann=7,-1,0
  4175.7    0.05       0  4434.1    0.12       0  4532.7    0.05       0
  4556.2    0.12       0  4829.9    0.05       0  5002.5    0.05       0
  5013.5    0.05       0
Bank Sta=5002.5,5013.5
Exp/Cntr=0.3,0.1

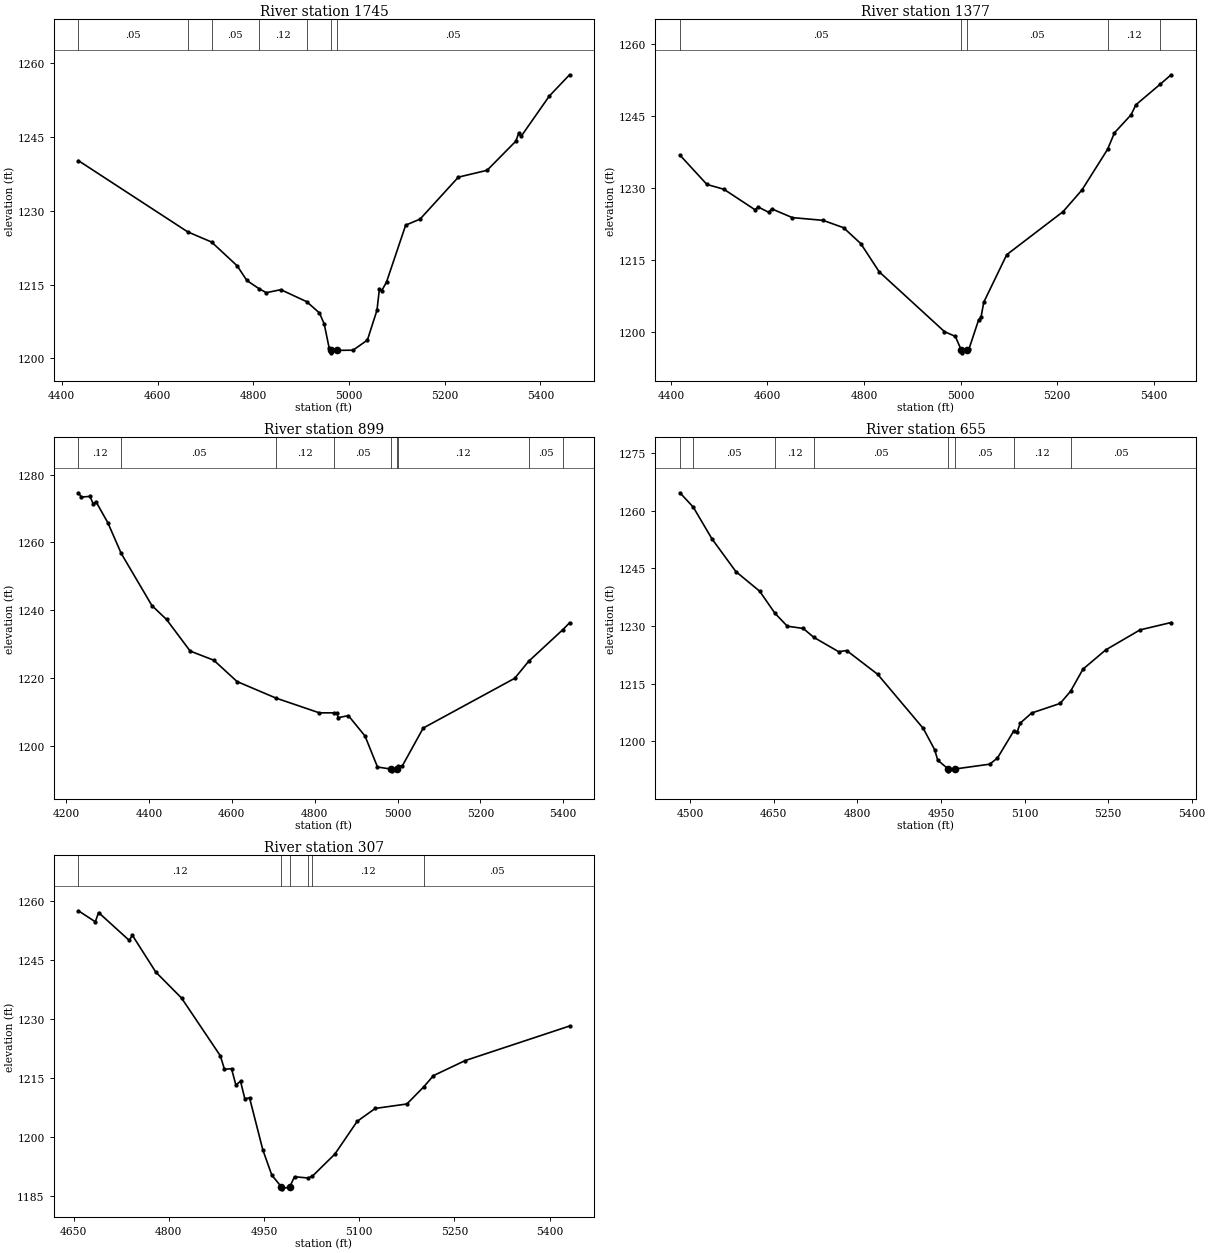
Type RM Length L Ch R = 1,1745,368,368,368
BEGIN DESCRIPTION:
GRAPE CREEK 4.0
END DESCRIPTION:
XS GIS Cut Line= 3
      2799242.54     10175882.49      2798780.70     10175802.62
      2798223.42     10175821.72
#Sta/Elev= 30
  4434.7 1240.21  4663.0 1225.72  4712.9 1223.65  4766.4 1218.81  4786.7 1215.82
  4812.3 1214.14  4827.3 1213.34  4857.7 1213.95  4911.7 1211.51  4938.4 1209.21
  4948.4 1206.95  4958.4 1202.18  4962.9 1201.60  4963.4 1201.10  4974.0 1201.60
  5008.5 1201.64  5038.5 1203.69  5058.5 1209.75  5063.6 1214.01  5068.6 1213.77
  5078.5 1215.51  5118.5 1227.08  5148.6 1228.31  5228.6 1236.85  5288.6 1238.24
  5348.7 1244.17  5354.7 1245.78  5359.7 1245.14  5418.7 1253.36  5461.0 1257.68
#Mann=7,-1,0
  4434.7    0.05       0  4663.0    0.12       0  4712.9    0.05       0
  4812.3    0.12       0  4911.7    0.05       0  4962.9    0.05       0
  4974.0    0.05       0
Bank Sta=4962.9,4974
Exp/Cntr=0.3,0.1

Type RM Length L Ch R = 1,1377,478,478,478
BEGIN DESCRIPTION:
GRAPE CREEK 3.0
END DESCRIPTION:
XS GIS Cut Line= 3
      2799239.06     10175788.76      2798958.70     10175485.89
      2798364.05     10175377.28
#Sta/Elev= 30
  4418.8 1236.87  4474.7 1230.74  4509.9 1229.73  4574.0 1225.47  4580.8 1226.03
  4602.3 1224.94  4609.1 1225.63  4651.6 1223.81  4715.1 1223.24  4757.7 1221.70
  4793.4 1218.37  4831.5 1212.48  4966.7 1199.98  4989.1 1198.99  5001.8 1196.05
  5002.3 1195.55  5012.9 1196.05  5017.6 1196.42  5037.3 1202.42  5042.4 1203.03
  5048.0 1206.12  5095.6 1216.06  5212.3 1225.06  5251.4 1229.59  5304.3 1238.05
  5318.7 1241.53  5353.0 1245.29  5363.2 1247.40  5412.9 1251.64  5436.0 1253.66
#Mann=5,-1,0
  4418.8    0.05       0  5001.8    0.03       0  5012.9    0.05       0
  5304.3    0.12       0  5412.9    0.05       0
Bank Sta=5001.8,5012.9
Exp/Cntr=0.3,0.1

Type RM Length L Ch R = 1,899,244,244,244
BEGIN DESCRIPTION:
GRAPE CREEK 2.0
END DESCRIPTION:
XS GIS Cut Line= 3
      2799455.71     10174503.09      2799049.80     10174981.44
      2798493.72     10175028.21
#Sta/Elev= 30
  4229.8 1274.61  4237.0 1273.34  4257.8 1273.55  4265.5 1271.31  4272.1 1272.00
  4300.7 1265.80  4333.1 1256.71  4407.2 1241.32  4442.4 1237.23  4499.5 1227.90
  4556.6 1225.19  4612.6 1218.91  4706.2 1214.04  4811.4 1209.66  4846.3 1209.67
  4854.3 1209.53  4856.5 1208.24  4881.4 1208.84  4921.5 1202.83  4951.6 1193.68
  4985.2 1193.05  4985.7 1192.55  4998.2 1193.05  5001.3 1193.93  5011.8 1194.07
  5062.0 1205.18  5282.8 1219.86  5316.3 1224.86  5398.9 1234.21  5415.2 1236.25
#Mann=9,-1,0
  4229.8    0.12       0  4333.1    0.05       0  4706.2    0.12       0
  4846.3    0.05       0  4985.2    0.03       0  4998.2    0.05       0
  5001.3    0.12       0  5316.3    0.05       0  5398.9    0.12       0
Bank Sta=4985.2,4998.2
Exp/Cntr=0.3,0.1

Type RM Length L Ch R = 1,655,348,348,348
BEGIN DESCRIPTION:
Mapping XS 7a5ed0bf
END DESCRIPTION:
XS GIS Cut Line= 3
      2799294.61     10174460.58      2799084.52     10174708.87
      2798541.15     10174826.92
#Sta/Elev= 30
  4481.7 1264.64  4505.6 1260.91  4539.1 1252.67  4582.0 1244.16  4624.8 1239.04
  4652.2 1233.30  4674.3 1229.95  4702.8 1229.36  4722.1 1227.03  4766.6 1223.30
  4780.8 1223.62  4836.5 1217.43  4918.3 1203.36  4938.8 1197.81  4944.3 1195.09
  4963.0 1192.83  4963.5 1192.33  4976.0 1192.83  5037.5 1194.06  5051.4 1195.66
  5080.5 1202.65  5086.6 1202.36  5092.3 1204.74  5112.8 1207.37  5163.9 1209.86
  5182.5 1213.00  5204.9 1218.78  5245.8 1223.79  5307.2 1228.98  5363.0 1230.90
#Mann=8,-1,0
  4481.7    0.12       0  4505.6    0.05       0  4652.2    0.12       0
  4722.1    0.05       0  4963.0    0.03       0  4976.0    0.05       0
  5080.5    0.12       0  5182.5    0.05       0
Bank Sta=4963,4976
Exp/Cntr=0.3,0.1

Type RM Length L Ch R = 1,307,0,0,0
BEGIN DESCRIPTION:
GRAPE CREEK 1.0
END DESCRIPTION:
XS GIS Cut Line= 4
      2799055.66     10174403.11      2798827.57     10174361.65
      2798581.05     10174632.48      2798515.07     10174795.69
#Sta/Elev= 30
  4657.5 1257.54  4684.2 1254.73  4689.2 1257.10  4737.5 1250.02  4742.6 1251.30
  4779.4 1241.95  4820.1 1235.32  4881.1 1220.65  4887.7 1217.19  4898.8 1217.36
  4905.6 1213.23  4913.0 1214.14  4919.8 1209.70  4927.2 1209.95  4948.1 1196.71
  4962.3 1190.26  4977.4 1187.27  4977.9 1186.77  4990.5 1187.27  4998.1 1189.85
  5019.2 1189.53  5026.2 1189.98  5061.7 1195.62  5096.8 1203.94  5125.2 1207.23
  5175.2 1208.37  5201.6 1212.70  5217.1 1215.59  5267.0 1219.41  5431.6 1228.21
#Mann=6,-1,0
  4657.5    0.12       0  4977.4    0.07       0  4990.5    0.12       0
  5019.2    0.05       0  5026.2    0.12       0  5201.6    0.05       0
Bank Sta=4977.4,4990.5
Exp/Cntr=0.3,0.1

Chan Stop Cuts=-1