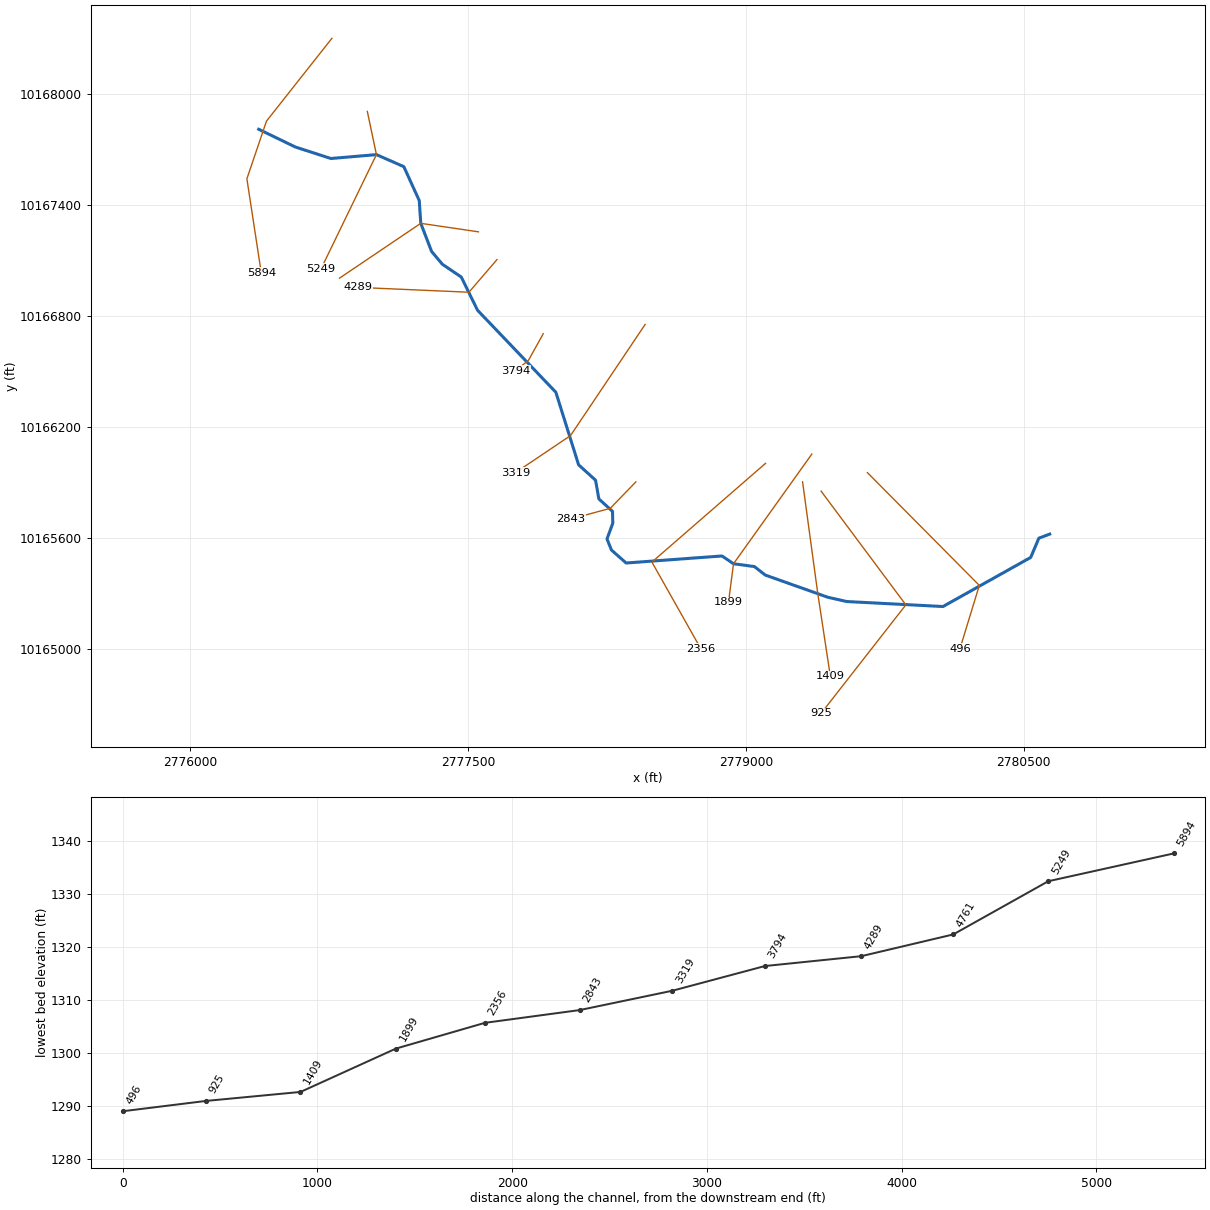
--- HELMS CREEK.prj (project) ---

Proj Title=HELMS CREEK Base Level Engineering
Current Plan=p01
Default Exp/Contr=0.3,0.1
English Units
Geom File=g01
Flow File=f01
Plan File=p01
Y Axis Title=Elevation
X Axis Title(PF)=Main Channel Distance
X Axis Title(XS)=Station
BEGIN DESCRIPTION:
HELMS CREEK
END DESCRIPTION:
DSS Export Rating Curves= 0
DSS Export Rating Curve Sorted= 0
DSS Export Volume Flow Curves= 0
DXF OffsetX= 0
DXF OffsetY= 0
DXF ScaleX= 1
DXF ScaleY= 10

--- HELMS CREEK.p01 (plan) ---

Plan Title=Multiple Run
Short Identifier=Multiple
Geom File=g01
Flow File=f01
Subcritical Flow
K Sum by GR= 0
Std Step Tol= 0.01
Critical Tol= 0.01
Num of Std Step Trials= 20
Max Error Tol= 0.3
Flow Tol Ratio= 0.001
Split Flow NTrial= 30
Split Flow Tol= 0.02
Split Flow Ratio= 0.02
Log Output Level= 0
Friction Slope Method= 1
Unsteady Friction Slope Method= 2
Unsteady Bridges Friction Slope Method= 1
Parabolic Critical Depth
Global Vel Dist=  1 , 1 , 1
Global Log Level= 0
CheckData=True
Encroach Param= -1, 0, 0, 0
BEGIN DESCRIPTION:
Multiple Run
END DESCRIPTION:

--- HELMS CREEK.f01 (steady flow) ---

Flow Title=Multiple
Number of Profiles=7
Profile Names=10-year,25-year,50-year,1pct_min,100-year,1pct_plu,500-year
River Rch & RM= HELMS CREEK,Reach-1,5894
    1613    2849    5718    4084    8318   16940   11864
River Rch & RM= HELMS CREEK,Reach-1,2356
    1803    3207    6483    4606    9467   19456   13489
Boundary for River Rch & Prof#=HELMS CREEK,Reach-1,1
Up Type=0
Dn Type=3
Dn Slope=0.005
Boundary for River Rch & Prof#=HELMS CREEK,Reach-1,2
Up Type=0
Dn Type=3
Dn Slope=0.005
Boundary for River Rch & Prof#=HELMS CREEK,Reach-1,3
Up Type=0
Dn Type=3
Dn Slope=0.005
Boundary for River Rch & Prof#=HELMS CREEK,Reach-1,4
Up Type=0
Dn Type=3
Dn Slope=0.005
Boundary for River Rch & Prof#=HELMS CREEK,Reach-1,5
Up Type=0
Dn Type=3
Dn Slope=0.005
Boundary for River Rch & Prof#=HELMS CREEK,Reach-1,6
Up Type=0
Dn Type=3
Dn Slope=0.005
Boundary for River Rch & Prof#=HELMS CREEK,Reach-1,7
Up Type=0
Dn Type=3
Dn Slope=0.005

--- HELMS CREEK.g01 (geometry) ---

Geom Title=Existing Conditions
Program Version=4.10

River Reach=HELMS CREEK     ,Reach-1
Reach XY= 30
        2776369.       10167807.      2776567.25       10167711.
        2776759.       10167649.      2777004.75       10167670.
      2777152.75       10167605.        2777236.       10167422.
      2777244.25       10167299.      2777302.75       10167147.
        2777361.       10167078.        2777463.       10167009.
       2777550.5       10166830.       2777973.5       10166387.
       2778096.5       10165995.        2778188.       10165912.
      2778205.75       10165811.       2778279.5       10165744.
        2778281.       10165680.      2778249.75       10165595.
      2778273.75       10165535.        2778353.       10165465.
       2778870.5       10165503.      2778932.75       10165461.
      2779045.25       10165446.        2779104.       10165400.
      2779442.25       10165280.      2779544.25       10165257.
      2780063.75       10165230.      2780537.25       10165495.
       2780581.5       10165599.        2780640.       10165621.

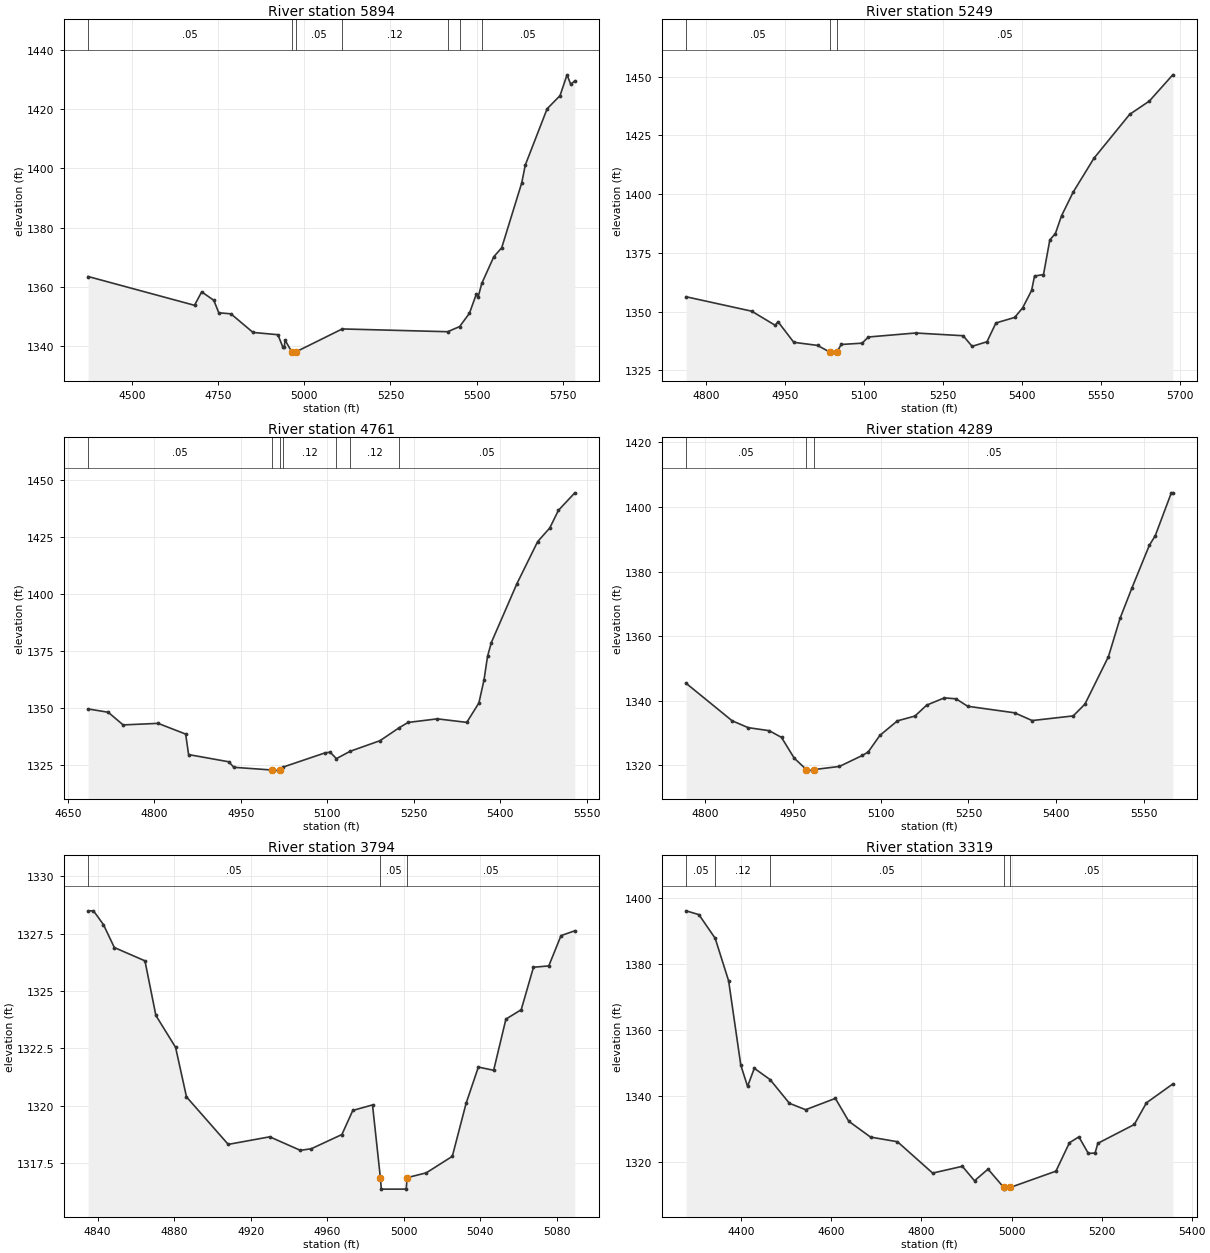
Type RM Length L Ch R = 1 ,5894    ,645,645,645
BEGIN DESCRIPTION:
HELMS CREEK 12.0
END DESCRIPTION:
XS GIS Cut Line= 4
      2776764.28     10168297.85      2776411.09     10167850.87
      2776305.34     10167539.58      2776383.16     10167030.74
#Sta/Elev= 30
  4372.2 1363.49  4681.1 1353.77  4701.9 1358.31  4737.2 1355.45  4751.6 1351.25
  4786.8 1350.89    4851 1344.61  4923.2 1343.84  4937.3 1339.75  4941.9 1339.75
    4944 1342.02  4963.2 1338.12  4963.7 1337.62  4976.9 1338.12    5110 1345.79
  5416.4 1344.85  5451.2 1346.61  5479.5  1351.1  5499.6 1357.59  5504.6  1356.5
  5515.2 1361.15  5550.3  1370.2  5573.1 1373.19  5631.3 1395.11  5641.6 1401.13
    5705 1420.13  5742.5 1424.57  5762.8  1431.6  5773.5 1428.39  5785.4 1429.55
#Mann= 7 ,-1 , 0
  4372.2     .05       0  4963.2     .07       0  4976.9     .05       0
    5110     .12       0  5416.4     .05       0  5451.2     .12       0
  5515.2     .05       0
Bank Sta=4963.2,4976.9
XS Rating Curve= 0 ,0
Exp/Cntr=0.3,0.1

Type RM Length L Ch R = 1 ,5249    ,488,488,488
BEGIN DESCRIPTION:
HELMS CREEK 11.0
END DESCRIPTION:
XS GIS Cut Line= 3
      2776955.69     10167903.09      2777004.75       10167670.
      2776705.67     10167053.08
#Sta/Elev= 30
  4761.8 1356.34  4886.3 1350.21  4931.1 1344.18  4936.2 1345.75  4966.2 1336.97
  5011.3 1335.66  5034.1 1332.87  5034.6 1332.37  5047.8 1332.87  5056.4 1336.05
    5096 1336.61  5107.7 1339.23  5197.4 1340.93  5287.7 1339.77  5304.7 1335.26
  5332.9 1337.21  5349.9  1345.2  5385.5 1347.55  5400.6 1351.62  5417.6 1359.03
  5423.2 1365.15  5440.2 1365.78  5452.2 1380.51  5462.8 1383.24  5474.4 1390.76
  5496.6 1400.88    5536 1415.26  5603.8 1433.92  5641.1 1439.57  5685.6 1450.73
#Mann= 3 ,-1 , 0
  4761.8     .05       0  5034.1     .07       0  5047.8     .05       0
Bank Sta=5034.1,5047.8
XS Rating Curve= 0 ,0
Exp/Cntr=0.3,0.1

Type RM Length L Ch R = 1 ,4761    ,472,472,472
BEGIN DESCRIPTION:
HELMS CREEK 10.0
END DESCRIPTION:
XS GIS Cut Line= 3
      2777555.69     10167253.11      2777244.25       10167299.
      2776805.72     10167003.14
#Sta/Elev= 30
  4685.2 1349.56    4720 1348.12  4745.9 1342.57  4806.5 1343.25  4854.3 1338.56
  4859.4 1329.58  4929.1 1326.42  4937.9    1324  5003.4 1322.83  5003.9 1322.33
  5017.2 1322.83  5023.9 1324.16  5095.9 1330.32  5104.8 1330.61  5115.6  1327.8
  5139.6 1331.03  5191.3 1335.67    5224 1341.25  5239.8 1343.65  5290.7 1345.23
  5341.7 1343.68  5362.7 1352.18  5371.6 1362.29  5377.7 1372.62  5384.3 1378.65
  5428.6 1404.42  5464.6 1422.86  5485.6 1428.83  5500.6 1436.56    5529 1444.22
#Mann= 7 ,-1 , 0
  4685.2     .05       0  5003.4     .05       0  5017.2     .05       0
  5023.9     .12       0  5115.6     .05       0  5139.6     .12       0
    5224     .05       0
Bank Sta=5003.4,5017.2
XS Rating Curve= 0 ,0
Exp/Cntr=0.3,0.1

Type RM Length L Ch R = 1 ,4289    ,495,495,495
BEGIN DESCRIPTION:
HELMS CREEK 9.0
END DESCRIPTION:
XS GIS Cut Line= 3
      2777655.71     10167103.14      2777504.25       10166927.
      2776905.72     10166953.11
#Sta/Elev= 30
  4767.7 1345.44  4846.2 1333.84  4873.6  1331.7  4909.8 1330.75  4930.7 1328.67
  4952.4 1322.25  4973.1 1318.73  4973.6 1318.23    4987 1318.73  5029.6 1319.68
  5068.6 1323.07  5078.6 1324.12  5098.7 1329.29  5128.7  1333.8  5158.7 1335.29
  5178.7 1338.67  5208.8 1340.91  5228.8 1340.63  5248.8 1338.31  5328.9 1336.29
  5358.9 1333.89    5429 1335.33    5449 1338.97  5489.2 1353.69    5509 1365.53
  5529.1 1374.86  5559.1 1388.18  5569.1 1391.11  5596.6 1404.41  5599.1 1404.41
#Mann= 3 ,-1 , 0
  4767.7     .05       0  4973.1     .03       0    4987     .05       0
Bank Sta=4973.1,4987
XS Rating Curve= 0 ,0
Exp/Cntr=0.3,0.1

Type RM Length L Ch R = 1 ,3794    ,475,475,475
BEGIN DESCRIPTION:
HELMS CREEK 8.0
END DESCRIPTION:
XS GIS Cut Line= 3
      2777905.68      10166703.1       2777825.5       10166559.
      2777755.71     10166503.13
#Sta/Elev= 30
  4835.1  1328.5  4837.9  1328.5  4843.1  1327.9  4848.8  1326.9  4864.8 1326.32
  4870.5 1323.94  4880.8 1322.55  4886.5 1320.39  4908.3 1318.32    4930 1318.65
    4946 1318.06  4951.7 1318.13  4967.7 1318.75  4973.4  1319.8  4983.7 1320.04
  4987.8 1316.87  4988.3 1316.37  5001.3 1316.37  5001.8 1316.87  5011.8 1317.08
  5025.4  1317.8  5032.6 1320.11    5039 1321.69    5047 1321.55  5053.4 1323.78
  5061.4 1324.19  5067.8 1326.04  5075.8  1326.1  5082.2 1327.42  5089.4 1327.63
#Mann= 3 ,-1 , 0
  4835.1     .05       0  4987.8     .05       0  5001.8     .05       0
Bank Sta=4987.8,5001.8
XS Rating Curve= 0 ,0
Exp/Cntr=0.3,0.1

Type RM Length L Ch R = 1 ,3319    ,476,476,476
BEGIN DESCRIPTION:
HELMS CREEK 7.0
END DESCRIPTION:
XS GIS Cut Line= 3
      2778455.66     10166753.08      2778052.75       10166153.
      2777755.65     10165953.09
#Sta/Elev= 30
  4277.2 1396.23  4305.7 1395.07  4341.8 1387.88  4371.7 1374.93  4398.7 1349.35
  4413.7 1342.92  4428.7 1348.41  4463.8 1344.97  4506.7 1337.77  4542.7 1335.83
  4608.7 1339.27  4638.5 1332.32  4686.8 1327.52  4746.7  1326.1  4824.8 1316.58
  4890.8 1318.64  4917.8 1314.25  4947.8 1317.79  4982.8 1312.21  4983.3 1311.71
  4996.9 1312.21  5098.6 1317.17  5128.6 1325.81  5149.6 1327.58  5170.6 1322.54
  5185.6 1322.69  5191.6 1325.62  5272.6 1331.34  5299.6 1337.92  5358.1 1343.65
#Mann= 5 ,-1 , 0
  4277.2     .05       0  4341.8     .12       0  4463.8     .05       0
  4982.8     .03       0  4996.9     .05       0
Bank Sta=4982.8,4996.9
XS Rating Curve= 0 ,0
Exp/Cntr=0.3,0.1

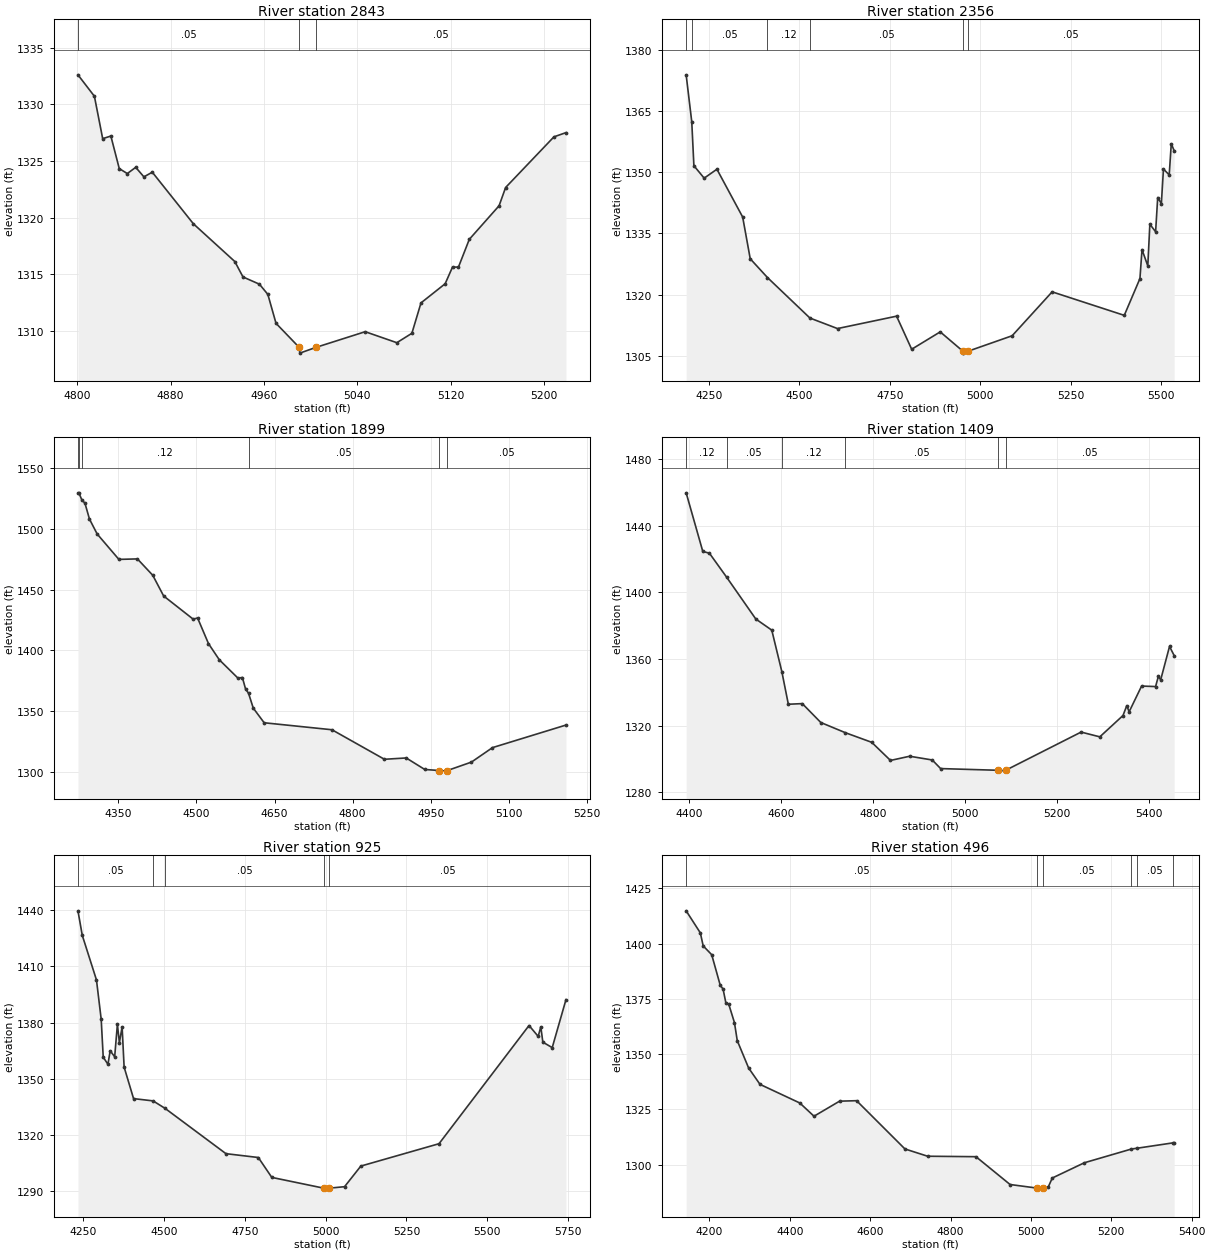
Type RM Length L Ch R = 1 ,2843    ,487,487,487
BEGIN DESCRIPTION:
HELMS CREEK 6.0
END DESCRIPTION:
XS GIS Cut Line= 3
       2778405.7     10165903.12        2778267.       10165760.
      2778055.72     10165703.12
#Sta/Elev= 30
  4800.7 1332.61  4814.8 1330.72  4821.9 1326.98  4828.9 1327.21  4836.1 1324.34
    4843  1323.9  4850.2 1324.45  4857.2 1323.61  4864.4 1324.02  4899.6 1319.47
  4935.1 1316.14  4942.1 1314.78  4956.2 1314.14  4963.4 1313.24  4970.4 1310.69
  4990.3 1308.56  4990.8 1308.06  5004.4 1308.56  5046.8 1309.95  5073.9 1308.98
  5086.8 1309.81  5094.6 1312.49  5115.3 1314.18  5121.6 1315.65  5126.7 1315.65
    5136  1318.1  5161.5 1321.06  5167.1 1322.67  5208.5 1327.14  5218.8 1327.51
#Mann= 3 ,-1 , 0
  4800.7     .05       0  4990.3     .05       0  5004.4     .05       0
Bank Sta=4990.3,5004.4
XS Rating Curve= 0 ,0
Exp/Cntr=0.3,0.1

Type RM Length L Ch R = 1 ,2356    ,457,457,457
BEGIN DESCRIPTION:
HELMS CREEK 5.0
END DESCRIPTION:
XS GIS Cut Line= 3
      2779105.67      10166003.1      2778492.25       10165470.
      2778755.69     10165003.09
#Sta/Elev= 30
  4187.3 1373.87  4202.8 1362.36  4208.7 1351.59  4237.1 1348.54  4272.3 1350.73
  4343.5 1339.01  4364.4 1328.78  4412.1 1324.17  4529.4 1314.25  4605.6 1311.67
  4768.9 1314.71  4810.6  1306.6  4889.5 1310.86  4951.9 1306.15  4952.4 1305.65
  4967.5 1306.15  5088.3 1309.91  5198.8 1320.67  5398.2 1314.91  5441.5 1323.93
  5447.2 1331.03  5463.2 1327.05  5468.9 1337.25  5484.8  1335.4  5490.6 1343.79
  5500.7 1342.31  5506.5 1350.77  5522.4 1349.34  5528.1 1356.98  5536.1 1355.27
#Mann= 6 ,-1 , 0
  4187.3     .12       0  4202.8     .05       0  4412.1     .12       0
  4529.4     .05       0  4951.9     .05       0  4967.5     .05       0
Bank Sta=4951.9,4967.5
XS Rating Curve= 0 ,0
Exp/Cntr=0.3,0.1

Type RM Length L Ch R = 1 ,1899    ,490,490,490
BEGIN DESCRIPTION:
HELMS CREEK 4.0
END DESCRIPTION:
XS GIS Cut Line= 3
      2779355.66     10166053.07      2778932.75       10165461.
      2778905.69     10165253.15
#Sta/Elev= 30
  4272.4 1529.62  4274.1 1529.62  4279.7 1524.02  4285.9 1521.02  4294.5 1508.08
  4309.2 1495.84    4351 1474.89  4386.6 1475.29  4416.1 1461.81    4437  1444.8
  4493.6 1425.77  4502.2  1426.7  4523.1 1405.63  4543.9 1392.33  4579.6  1377.3
  4588.2 1377.76  4594.3 1368.35    4600 1364.82  4609.1  1352.6    4630 1340.56
  4760.2 1334.81    4861 1310.53  4902.8 1311.62  4938.4 1302.16  4966.2 1301.29
  4966.7 1300.79  4981.9 1301.29  5028.1 1308.22  5068.5 1320.12  5209.6 1338.67
#Mann= 6 ,-1 , 0
  4272.4     .12       0  4274.1     .05       0  4279.7     .12       0
    4600     .05       0  4966.2     .05       0  4981.9     .05       0
Bank Sta=4966.2,4981.9
XS Rating Curve= 0 ,0
Exp/Cntr=0.3,0.1

Type RM Length L Ch R = 1 ,1409    ,484,484,484
BEGIN DESCRIPTION:
HELMS CREEK 3.0
END DESCRIPTION:
XS GIS Cut Line= 3
      2779305.68     10165903.16       2779387.5       10165302.
      2779455.68     10164853.15
#Sta/Elev= 30
  4393.3 1459.76  4429.5 1424.53  4443.8 1423.52  4481.4 1409.04  4544.7 1383.97
  4579.4 1377.29  4601.3 1352.34  4615.4 1332.78  4645.7 1333.16    4686 1321.81
  4739.5 1315.67  4796.6 1309.92  4837.4 1299.03  4879.1 1301.55  4928.2  1299.3
  4946.4 1294.14  5071.9 1293.11  5072.4 1292.61  5087.7 1293.11  5251.7 1316.06
  5292.4  1313.2  5342.8 1326.02    5351 1331.95  5356.1 1328.24  5383.2  1343.7
  5413.6  1343.4  5419.7 1349.57  5424.7 1347.47  5443.9  1367.5    5454 1362.02
#Mann= 6 ,-1 , 0
  4393.3     .12       0  4481.4     .05       0  4601.3     .12       0
  4739.5     .05       0  5071.9     .03       0  5087.7     .05       0
Bank Sta=5071.9,5087.7
XS Rating Curve= 0 ,0
Exp/Cntr=0.3,0.1

Type RM Length L Ch R = 1 ,925     ,429,429,429
BEGIN DESCRIPTION:
HELMS CREEK 2.0
END DESCRIPTION:
XS GIS Cut Line= 3
       2779405.7     10165853.09      2779863.25       10165239.
      2779405.68     10164653.11
#Sta/Elev= 30
  4234.2 1439.73  4247.7 1426.56  4291.5 1402.77  4306.1 1381.77  4312.4 1361.45
    4327 1357.68  4333.9 1364.91  4347.8 1361.69  4356.2 1378.98  4362.4 1369.26
  4370.8  1377.7    4377 1356.18  4406.2 1339.32  4466.6  1338.1  4503.6 1334.11
  4691.9 1309.88    4792 1307.83  4833.7 1297.19  4994.7 1291.42  4995.2 1290.92
  5010.5 1291.42  5058.7 1292.22    5109 1303.24  5350.9 1315.21  5629.2 1378.41
  5657.5  1372.6  5665.6 1377.71  5671.9 1369.51  5700.9 1366.59  5743.4 1392.23
#Mann= 5 ,-1 , 0
  4234.2     .05       0  4466.6     .12       0  4503.6     .05       0
  4994.7     .03       0  5010.5     .05       0
Bank Sta=4994.7,5010.5
XS Rating Curve= 0 ,0
Exp/Cntr=0.3,0.1

Type RM Length L Ch R = 1 ,496     ,0,0,0
BEGIN DESCRIPTION:
HELMS CREEK 1.0
END DESCRIPTION:
XS GIS Cut Line= 3
       2779655.7     10165953.09        2780260.       10165344.
      2780155.68      10165003.1
#Sta/Elev= 30
    4142 1414.86  4177.3 1404.88  4184.4    1399  4205.6 1395.01  4226.8  1381.2
  4233.9 1379.47  4240.9 1373.16    4248 1372.62  4262.2 1364.29  4269.2 1356.13
  4297.5 1343.75  4325.8 1336.36  4424.8 1327.94  4460.2 1321.95  4523.8 1328.76
  4566.2 1328.97  4686.5 1307.14    4743 1303.85  4863.2 1303.64  4948.1 1291.06
  5013.9 1289.47  5014.4 1288.97  5029.8 1289.47  5042.8  1289.8  5053.2    1294
    5133  1300.9  5250.3 1307.12  5264.2 1307.47  5354.4 1309.92  5356.5 1309.92
#Mann= 6 ,-1 , 0
    4142     .05       0  5013.9     .05       0  5029.8     .05       0
  5250.3     .12       0  5264.2     .05       0  5354.4     .12       0
Bank Sta=5013.9,5029.8
XS Rating Curve= 0 ,0
Exp/Cntr=0.3,0.1

Chan Stop Cuts=-1
Use User Specified Reach Order=0
Composite Channel Slope=5