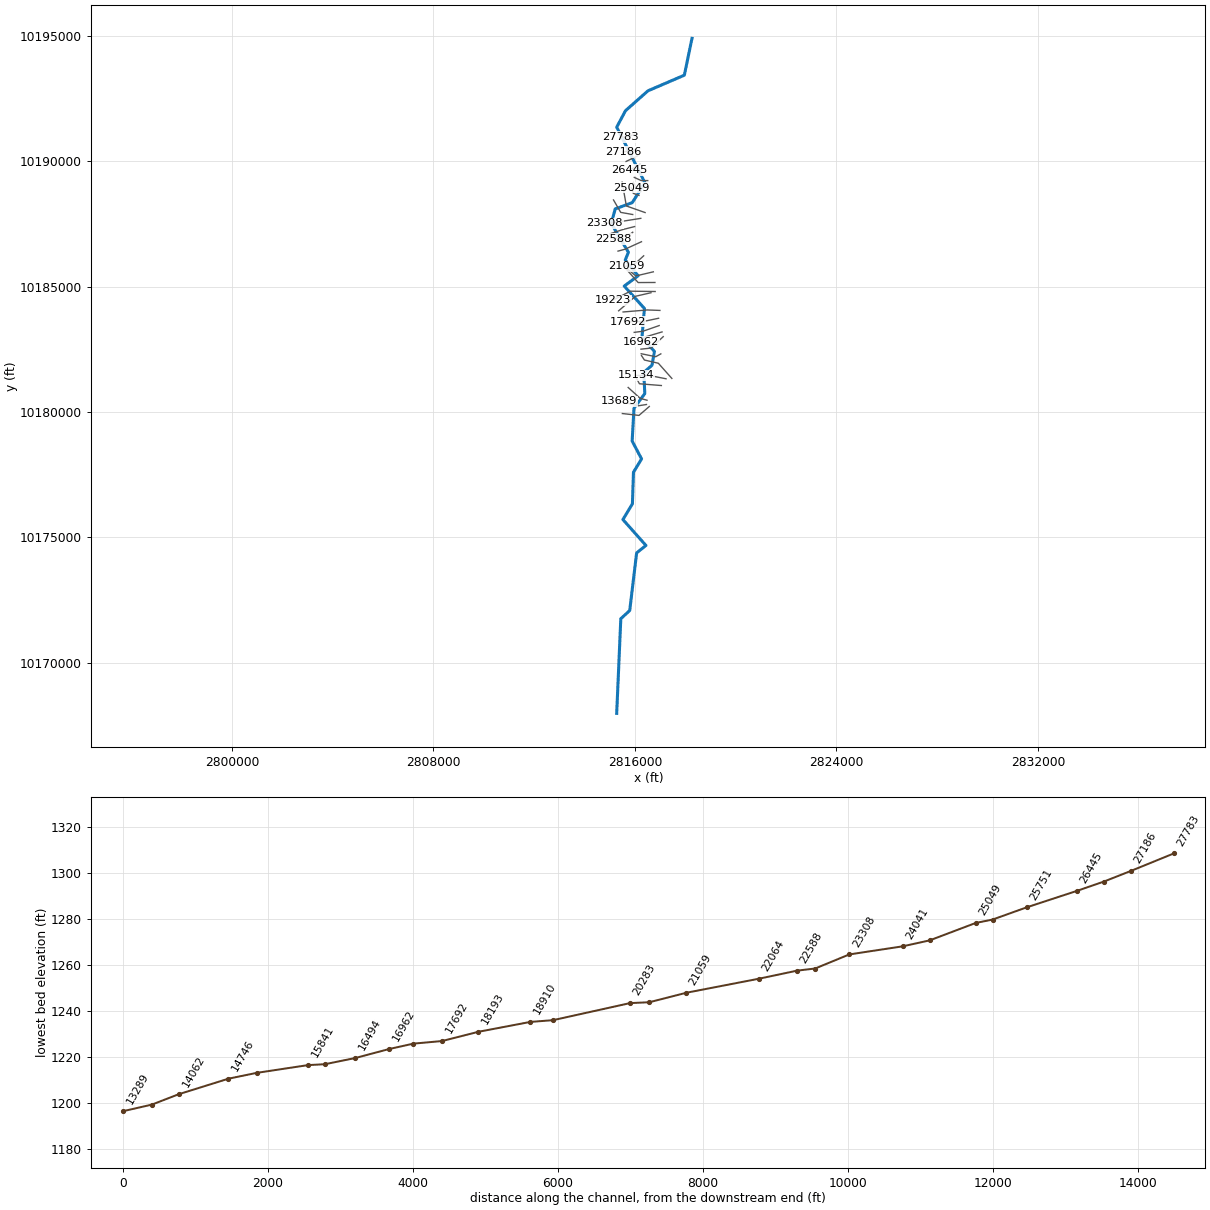
--- HONDO CREEK.prj (project) ---

Proj Title=HONDO CREEK Base Level Engineering
Current Plan=p01
Default Exp/Contr=0.3,0.1
English Units
Geom File=g01
Flow File=f01
Plan File=p01
Y Axis Title=Elevation
X Axis Title(PF)=Main Channel Distance
X Axis Title(XS)=Station
BEGIN DESCRIPTION:
HONDO CREEK
END DESCRIPTION:
DSS Export Rating Curves= 0
DSS Export Rating Curve Sorted= 0
DSS Export Volume Flow Curves= 0
DXF OffsetX= 0
DXF OffsetY= 0
DXF ScaleX= 1
DXF ScaleY= 10

--- HONDO CREEK.p01 (plan) ---

Plan Title=Multiple Run
Short Identifier=Multiple
Geom File=g01
Flow File=f01
Subcritical Flow
K Sum by GR= 0
Std Step Tol= 0.01
Critical Tol= 0.01
Num of Std Step Trials= 20
Max Error Tol= 0.3
Flow Tol Ratio= 0.001
Split Flow NTrial= 30
Split Flow Tol= 0.02
Split Flow Ratio= 0.02
Log Output Level= 0
Friction Slope Method= 1
Unsteady Friction Slope Method= 2
Unsteady Bridges Friction Slope Method= 1
Parabolic Critical Depth
Global Vel Dist=  1 , 1 , 1
Global Log Level= 0
CheckData=True
Encroach Param= -1, 0, 0, 0
BEGIN DESCRIPTION:
Multiple Run
END DESCRIPTION:

--- HONDO CREEK.f01 (steady flow) ---

Flow Title=Multiple
Program Version=4.10
Number of Profiles= 7
Profile Names=10-year,25-year,50-year,1pct_min,100-year,1pct_plu,500-year
River Rch & RM=HONDO CREEK,Reach-1         ,27783
     666    1102    2377    1918    3382    5961    4870
River Rch & RM=HONDO CREEK,Reach-1         ,23308
     878    1481    3066    2374    4381    8084    6269
River Rch & RM=HONDO CREEK,Reach-1         ,19223
    1212    2088    3371    2446    4711    9073    6493
River Rch & RM=HONDO CREEK,Reach-1         ,15841
    1955    3484    5737    3983    8163   16729   11252
River Rch & RM=HONDO CREEK,Reach-1         ,15134
    1955    3484    5737    3983    8163   16729   11252
River Rch & RM=HONDO CREEK,Reach-1         ,4380
    2074    3718    6037    4129    8604   17927   11865
River Rch & RM=HONDO CREEK,Reach-1         ,933
    4018    7554   13658    9544   19914   41550   27285
Boundary for River Rch & Prof#=HONDO CREEK,Reach-1         , 1
Up Type= 0
Dn Type= 3
Dn Slope=0.005
Boundary for River Rch & Prof#=HONDO CREEK,Reach-1         , 2
Up Type= 0
Dn Type= 3
Dn Slope=0.005
Boundary for River Rch & Prof#=HONDO CREEK,Reach-1         , 3
Up Type= 0
Dn Type= 3
Dn Slope=0.005
Boundary for River Rch & Prof#=HONDO CREEK,Reach-1         , 4
Up Type= 0
Dn Type= 3
Dn Slope=0.005
Boundary for River Rch & Prof#=HONDO CREEK,Reach-1         , 5
Up Type= 0
Dn Type= 3
Dn Slope=0.005
Boundary for River Rch & Prof#=HONDO CREEK,Reach-1         , 6
Up Type= 0
Dn Type= 3
Dn Slope=0.005
Boundary for River Rch & Prof#=HONDO CREEK,Reach-1         , 7
Up Type= 0
Dn Type= 3
Dn Slope=0.005
DSS Import GetInterval= 0
DSS Import GetPeak= 0
DSS Import FillOption= 0

--- HONDO CREEK.g01 (geometry) ---

Geom Title=Existing Conditions
Program Version=4.10

River Reach=HONDO CREEK     ,Reach-1
Reach XY= 30
       2818267.5       10194905.      2817963.75       10193434.
        2816521.       10192812.        2815627.       10192017.
        2815279.       10191360.      2816397.75       10189145.
        2815896.       10188349.      2815218.75       10188099.
        2815063.       10187516.      2815742.25       10186367.
       2815617.5       10186057.        2816130.       10185431.
        2815577.       10185020.      2816380.25       10184125.
      2816281.25       10182969.      2816776.75       10182411.
      2816679.75       10181860.      2816351.75       10181575.
      2816394.25       10180730.      2815964.75       10180148.
       2815891.5       10178837.      2816265.25       10178123.
        2815944.       10177592.        2815902.       10176332.
      2815524.75       10175704.      2816439.25       10174671.
       2816069.5       10174374.        2815795.       10172073.
        2815441.       10171747.        2815278.       10167970.

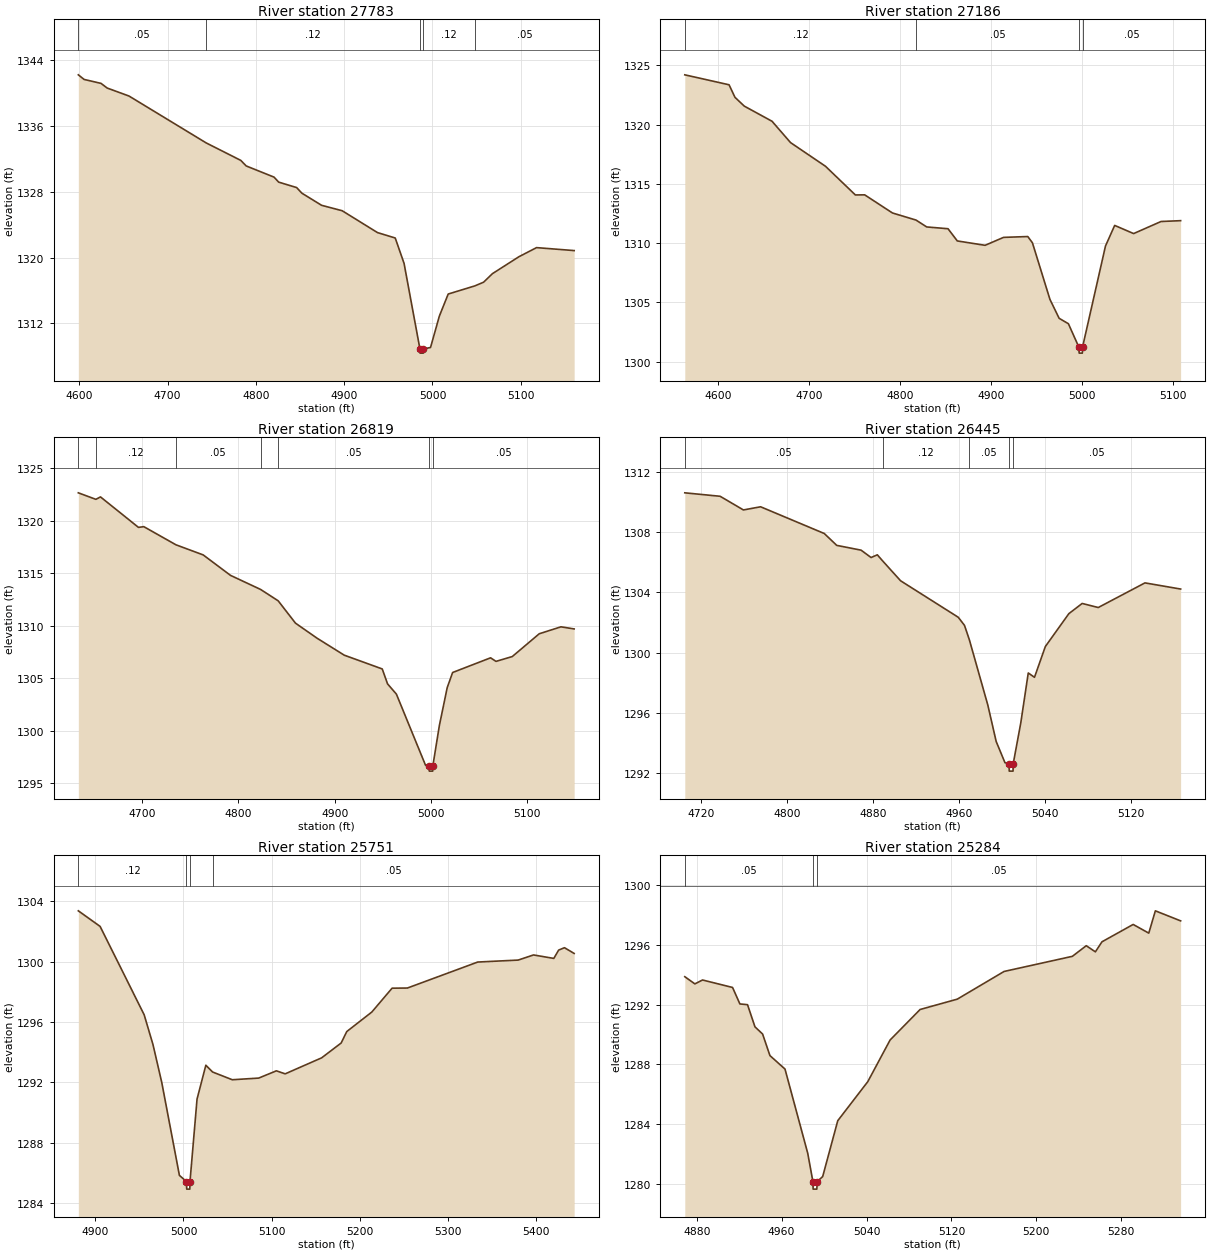
Type RM Length L Ch R = 1 ,27783   ,597,597,597
BEGIN DESCRIPTION:
HONDO CREEK 55.0
END DESCRIPTION:
XS GIS Cut Line= 3
      2815970.06     10191069.09        2815707.     10190980.53
      2815423.16     10190967.51
#Sta/Elev= 30
  4598.8 1342.25  4605.3 1341.69  4624.5 1341.21  4631.5 1340.64  4656.2 1339.67
  4743.7 1333.96  4782.8 1331.84    4789 1331.16  4820.5  1329.8  4825.8 1329.19
  4846.1 1328.53    4852 1327.85  4874.4 1326.37  4897.7 1325.71  4937.7 1323.05
  4957.8 1322.39  4967.8 1319.31  4985.8 1308.88    4986 1308.38  4989.5 1308.38
  4989.8 1308.88  4997.8 1309.07  5007.8 1312.89  5017.8 1315.57  5047.9 1316.56
  5057.9 1317.01  5067.9 1318.05  5097.9 1320.11  5117.9 1321.22  5160.5 1320.86
#Mann= 5 ,-1 , 0
  4598.8     .05       0  4743.7     .12       0  4985.8     .07       0
  4989.8     .12       0  5047.9     .05       0
Bank Sta=4985.8,4989.8
XS Rating Curve= 0 ,0
Exp/Cntr=0.3,0.1

Type RM Length L Ch R = 1 ,27186   ,367,367,367
BEGIN DESCRIPTION:
HONDO CREEK 54.0
END DESCRIPTION:
XS GIS Cut Line= 2
      2816059.89     10190466.66      2815524.52      10190367.9
#Sta/Elev= 30
  4563.8 1324.21  4612.4 1323.37  4618.9 1322.31  4629.1 1321.57  4659.6 1320.29
  4679.9 1318.49  4718.3 1316.49  4751.1 1314.07  4761.3 1314.08  4791.8 1312.55
  4817.7 1311.95  4829.4 1311.37  4852.8 1311.22    4863 1310.19  4893.5 1309.82
  4913.8 1310.49  4940.4 1310.56  4945.5 1310.03  4964.7 1305.26  4974.8 1303.66
    4985  1303.2  4996.5 1301.22  4996.8 1300.72  5000.3 1300.72  5000.5 1301.22
  5025.7 1309.76  5035.8  1311.5  5056.6 1310.81  5086.7 1311.83  5108.2  1311.9
#Mann= 4 ,-1 , 0
  4563.8     .12       0  4817.7     .05       0  4996.5     .05       0
  5000.5     .05       0
Bank Sta=4996.5,5000.5
XS Rating Curve= 0 ,0
Exp/Cntr=0.3,0.1

Type RM Length L Ch R = 1 ,26819   ,374,374,374
BEGIN DESCRIPTION:
HONDO CREEK 53.0
END DESCRIPTION:
XS GIS Cut Line= 2
      2816111.93     10190217.94       2815650.2     10189991.19
#Sta/Elev= 30
  4634.1 1322.67  4652.3 1322.05  4657.1 1322.28  4696.5 1319.38    4702 1319.45
  4735.4 1317.72  4763.6 1316.76    4792 1314.81  4823.2 1313.47  4841.4 1312.39
  4859.4 1310.26  4881.9 1308.82    4910 1307.21  4949.4  1305.9  4954.9 1304.48
  4964.1  1303.5  4994.3 1296.73  4997.9 1296.67  4998.2 1296.17  5001.7 1296.17
  5001.9 1296.67  5008.7 1300.53  5016.8 1304.12  5022.4 1305.56  5061.8 1306.96
  5067.4 1306.62  5084.3 1307.08  5112.3 1309.25  5134.8 1309.91  5148.5 1309.71
#Mann= 7 ,-1 , 0
  4634.1     .05       0  4652.3     .12       0  4735.4     .05       0
  4823.2     .12       0  4841.4     .05       0  4997.9     .05       0
  5001.9     .05       0
Bank Sta=4997.9,5001.9
XS Rating Curve= 0 ,0
Exp/Cntr=0.3,0.1

Type RM Length L Ch R = 1 ,26445   ,694,694,694
BEGIN DESCRIPTION:
HONDO CREEK 52.0
END DESCRIPTION:
XS GIS Cut Line= 2
      2816199.19      10189874.2      2815795.57     10189649.82
#Sta/Elev= 30
  4704.8 1310.64  4737.7 1310.41  4759.4  1309.5  4775.4 1309.71  4834.7 1307.93
  4846.3 1307.14    4869 1306.82  4878.3 1306.33  4884.1 1306.51  4889.5 1306.07
  4905.8 1304.78  4959.5 1302.35  4965.3 1301.81  4969.8 1300.86    4987 1296.51
  4994.8 1294.08    5003 1292.66  5006.7  1292.6    5007  1292.1  5010.5  1292.1
  5010.7  1292.6  5017.7  1295.3  5024.7 1298.64  5030.5 1298.35  5040.6  1300.4
  5062.5 1302.59  5074.9 1303.27  5089.9    1303  5133.4 1304.64  5166.6 1304.23
#Mann= 5 ,-1 , 0
  4704.8     .05       0  4889.5     .12       0  4969.8     .05       0
  5006.7     .05       0  5010.7     .05       0
Bank Sta=5006.7,5010.7
XS Rating Curve= 0 ,0
Exp/Cntr=0.3,0.1

Type RM Length L Ch R = 1 ,25751   ,467,467,467
BEGIN DESCRIPTION:
HONDO CREEK 51.0
END DESCRIPTION:
XS GIS Cut Line= 3
      2816510.42     10189229.24      2816249.99     10189229.24
      2815975.68     10189355.98
#Sta/Elev= 30
  4880.7 1303.36  4905.4 1302.33  4955.4 1296.48  4965.4 1294.51  4975.4 1291.99
  4995.4 1285.85  5003.4 1285.44  5003.7 1284.94  5007.2 1284.94  5007.4 1285.44
  5015.4  1290.9  5025.4 1293.14  5033.1 1292.69  5055.4 1292.18  5085.4 1292.29
  5105.4 1292.77  5115.4 1292.57  5156.8 1293.63  5178.9 1294.61  5185.3 1295.37
  5213.7 1296.66  5236.7 1298.24  5254.1 1298.25  5333.9 1299.97  5379.8  1300.1
  5397.2 1300.44  5420.2 1300.21  5425.7 1300.76  5432.3 1300.92  5443.3 1300.54
#Mann= 4 ,-1 , 0
  4880.7     .12       0  5003.4     .07       0  5007.4     .12       0
  5033.1     .05       0
Bank Sta=5003.4,5007.4
XS Rating Curve= 0 ,0
Exp/Cntr=0.3,0.1

Type RM Length L Ch R = 1 ,25284   ,235,235,235
BEGIN DESCRIPTION:
HONDO CREEK 50.0
END DESCRIPTION:
XS GIS Cut Line= 3
      2816234.35     10188788.28      2816067.01     10188963.01
      2815935.73     10189145.94
#Sta/Elev= 30
  4868.8 1293.86  4878.3 1293.38  4885.5 1293.64  4913.8 1293.14  4920.7 1292.04
  4927.9 1291.99  4934.9 1290.51  4942.1 1290.03    4949 1288.59  4963.2 1287.69
  4984.6 1282.07  4989.5 1280.17  4989.7 1279.67  4993.2 1279.67  4993.5 1280.17
  4998.7 1280.51  5012.9 1284.24  5041.2 1286.85  5062.2 1289.63  5090.5 1291.67
  5125.5 1292.36  5169.6 1294.21  5233.9 1295.22    5247 1295.93  5255.6 1295.52
  5261.8 1296.19  5291.2 1297.35  5305.9 1296.77  5312.1 1298.26  5335.9 1297.59
#Mann= 3 ,-1 , 0
  4868.8     .05       0  4989.5     .05       0  4993.5     .05       0
Bank Sta=4989.5,4993.5
XS Rating Curve= 0 ,0
Exp/Cntr=0.3,0.1

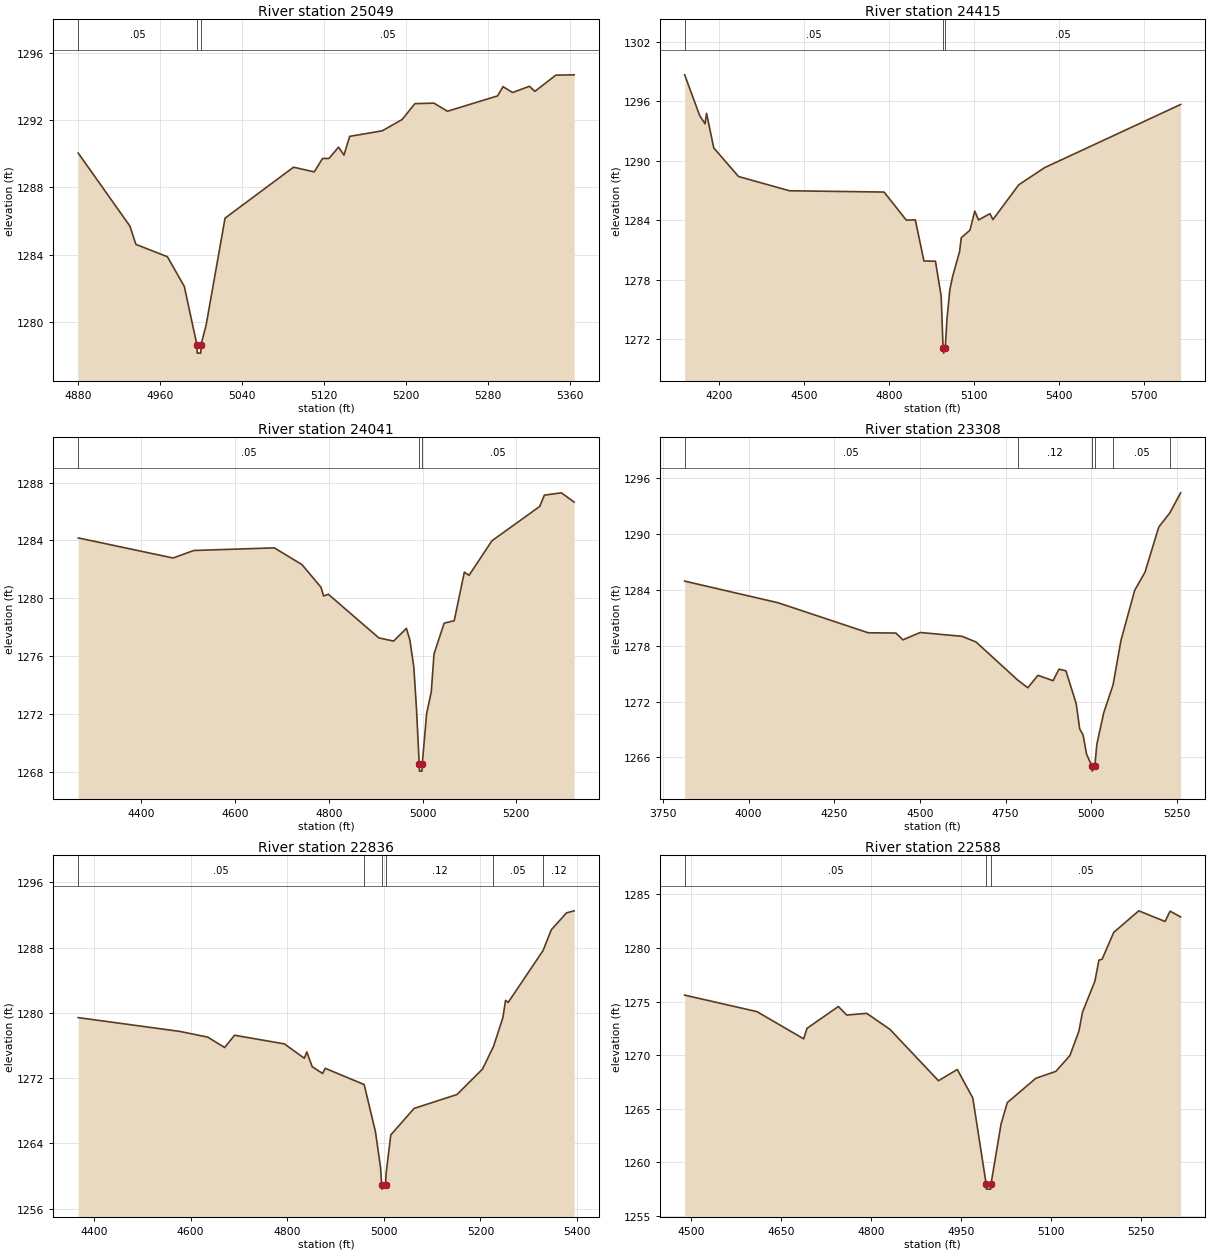
Type RM Length L Ch R = 1 ,25049   ,634,634,634
BEGIN DESCRIPTION:
HONDO CREEK 49.0
END DESCRIPTION:
XS GIS Cut Line= 3
      2816163.17     10188638.97      2815936.81     10188719.99
      2815856.46     10188949.83
#Sta/Elev= 30
  4880.2 1290.04  4930.6 1285.71  4936.5 1284.62  4967.2 1283.89  4983.7 1282.13
    4996 1278.67  4996.3 1278.17  4999.8 1278.17    5000 1278.67    5005 1279.83
  5023.5 1286.18  5090.3  1289.2  5110.5 1288.92  5118.6 1289.72  5124.9 1289.72
  5134.2 1290.39  5139.5 1289.92  5145.1 1291.03  5176.9 1291.36  5196.3 1292.03
  5208.7 1292.97  5227.3    1293  5240.5 1292.52  5289.4 1293.43  5294.7 1293.98
    5304 1293.63  5320.5    1294  5325.8  1293.7  5346.2 1294.66  5364.1 1294.68
#Mann= 3 ,-1 , 0
  4880.2     .05       0    4996     .05       0    5000     .05       0
Bank Sta=4996,5000
XS Rating Curve= 0 ,0
Exp/Cntr=0.3,0.1

Type RM Length L Ch R = 1 ,24415   ,374,374,374
BEGIN DESCRIPTION:
HONDO CREEK 48.0
END DESCRIPTION:
XS GIS Cut Line= 3
      2816405.73      10187953.1      2815662.92     10188215.75
      2815493.05     10189166.72
#Sta/Elev= 30
    4077 1298.68  4130.1 1294.57    4149 1293.75  4154.3  1294.8  4179.9 1291.31
  4267.3 1288.43  4447.5 1286.99  4782.2 1286.86  4860.8 1284.03  4892.7 1284.06
  4923.1 1279.91  4963.8 1279.89  4984.1 1276.38  4990.2 1271.61  4992.1 1271.12
  4992.6 1270.62  4998.5 1271.12  5004.4 1273.98  5014.6 1276.99  5024.7 1278.37
  5049.2 1280.86  5055.2 1282.26  5085.7 1283.01    5103 1284.94  5116.2 1284.05
  5156.8 1284.68    5167 1284.08  5258.4 1287.59  5349.8 1289.32  5830.9 1295.69
#Mann= 3 ,-1 , 0
    4077     .05       0  4992.1     .05       0  4998.5     .05       0
Bank Sta=4992.1,4998.5
XS Rating Curve= 0 ,0
Exp/Cntr=0.3,0.1

Type RM Length L Ch R = 1 ,24041   ,733,733,733
BEGIN DESCRIPTION:
HONDO CREEK 47.0
END DESCRIPTION:
XS GIS Cut Line= 3
      2815914.93     10187875.07      2815437.49     10187960.15
      2815151.03     10188456.68
#Sta/Elev= 30
  4265.1 1284.17  4467.5 1282.78  4511.8  1283.3  4683.7 1283.48  4742.6 1282.32
    4783 1280.76  4788.8 1280.15  4798.8 1280.27  4906.6 1277.25  4938.1 1277.03
  4965.4 1277.91  4972.8  1277.1  4981.2 1275.24    4987 1272.28  4992.7 1268.53
  4993.2 1268.03  4998.7 1268.03  4999.2 1268.53  5008.5    1272  5018.5 1273.53
  5024.3 1276.14  5045.9 1278.27  5067.4 1278.44    5089  1281.8    5099 1281.58
  5147.8 1283.97  5249.9 1286.35  5259.8 1287.13  5296.1 1287.29  5323.3 1286.65
#Mann= 3 ,-1 , 0
  4265.1     .05       0  4992.7     .05       0  4999.2     .05       0
Bank Sta=4992.7,4999.2
XS Rating Curve= 0 ,0
Exp/Cntr=0.3,0.1

Type RM Length L Ch R = 1 ,23308   ,472,472,472
BEGIN DESCRIPTION:
HONDO CREEK 46.0
END DESCRIPTION:
XS GIS Cut Line= 3
      2816234.33     10187722.29      2815175.34     10187552.16
      2814802.11     10187520.91
#Sta/Elev= 30
  3813.7 1284.95  4085.8 1282.63  4349.3  1279.4  4430.1 1279.37  4450.4 1278.64
    4501 1279.43  4622.6 1279.02  4663.9 1278.41    4785 1274.33    4815 1273.49
  4844.5 1274.83  4888.6 1274.25    4906 1275.49  4926.1 1275.31  4956.2 1271.78
  4966.2 1269.08  4976.2 1268.42  4986.3 1266.36  5002.3 1265.03  5002.8 1264.53
  5010.4 1265.03  5016.4 1267.42  5036.4 1270.79  5063.6 1273.79  5086.6 1278.55
  5126.8 1283.97  5156.9 1285.91    5197 1290.76    5229 1292.27  5260.8 1294.44
#Mann= 6 ,-1 , 0
  3813.7     .05       0    4785     .12       0  5002.3     .07       0
  5010.4     .12       0  5063.6     .05       0    5229     .12       0
Bank Sta=5002.3,5010.4
XS Rating Curve= 0 ,0
Exp/Cntr=0.3,0.1

Type RM Length L Ch R = 1 ,22836   ,248,248,248
BEGIN DESCRIPTION:
HONDO CREEK 45.0
END DESCRIPTION:
XS GIS Cut Line= 3
      2815989.53     10187394.16      2815519.17     10187275.16
       2815005.7     10187103.12
#Sta/Elev= 30
  4367.3 1279.42  4577.6 1277.73  4635.4 1277.03  4670.4 1275.76    4691 1277.26
  4794.2  1276.2  4835.4 1274.44  4840.5 1275.21  4851.7 1273.41  4873.3 1272.57
  4878.6 1273.21  4959.3 1271.22  4982.7 1265.43  4993.3 1261.02  4995.5 1258.91
    4996 1258.41  5003.6 1258.91  5004.8 1260.39  5014.4 1265.05  5062.7  1268.3
  5151.5    1270  5204.2 1273.11  5226.9 1275.87  5246.4  1279.4    5252 1281.53
  5257.3 1281.27  5329.6 1287.63  5346.7 1290.18  5378.2 1292.25    5394  1292.5
#Mann= 6 ,-1 , 0
  4367.3     .05       0  4959.3     .12       0  4995.5     .07       0
  5003.6     .12       0  5226.9     .05       0  5329.6     .12       0
Bank Sta=4995.5,5003.6
XS Rating Curve= 0 ,0
Exp/Cntr=0.3,0.1

Type RM Length L Ch R = 1 ,22588   ,524,524,524
BEGIN DESCRIPTION:
HONDO CREEK 44.0
END DESCRIPTION:
XS GIS Cut Line= 3
      2815914.33     10187167.67      2815829.85     10187104.24
      2815138.88     10186899.89
#Sta/Elev= 30
  4489.5  1275.6  4609.9 1274.06  4687.7 1271.52  4693.3  1272.5  4745.5 1274.54
  4759.5 1273.74  4792.7  1273.9  4831.2 1272.42  4912.3 1267.61  4943.6 1268.66
  4969.5    1266  4991.7 1257.99  4992.2 1257.49  4999.4 1257.49  4999.9 1257.99
  5016.6 1263.58    5027 1265.57  5074.6 1267.84  5107.8 1268.48  5131.3 1269.96
  5146.3 1272.25  5152.2    1274    5173 1276.92  5179.6 1278.87  5184.8 1278.94
  5204.3 1281.46    5246 1283.47  5289.8 1282.48  5298.2 1283.44  5315.7  1282.9
#Mann= 3 ,-1 , 0
  4489.5     .05       0  4991.7     .05       0  4999.9     .05       0
Bank Sta=4991.7,4999.9
XS Rating Curve= 0 ,0
Exp/Cntr=0.3,0.1

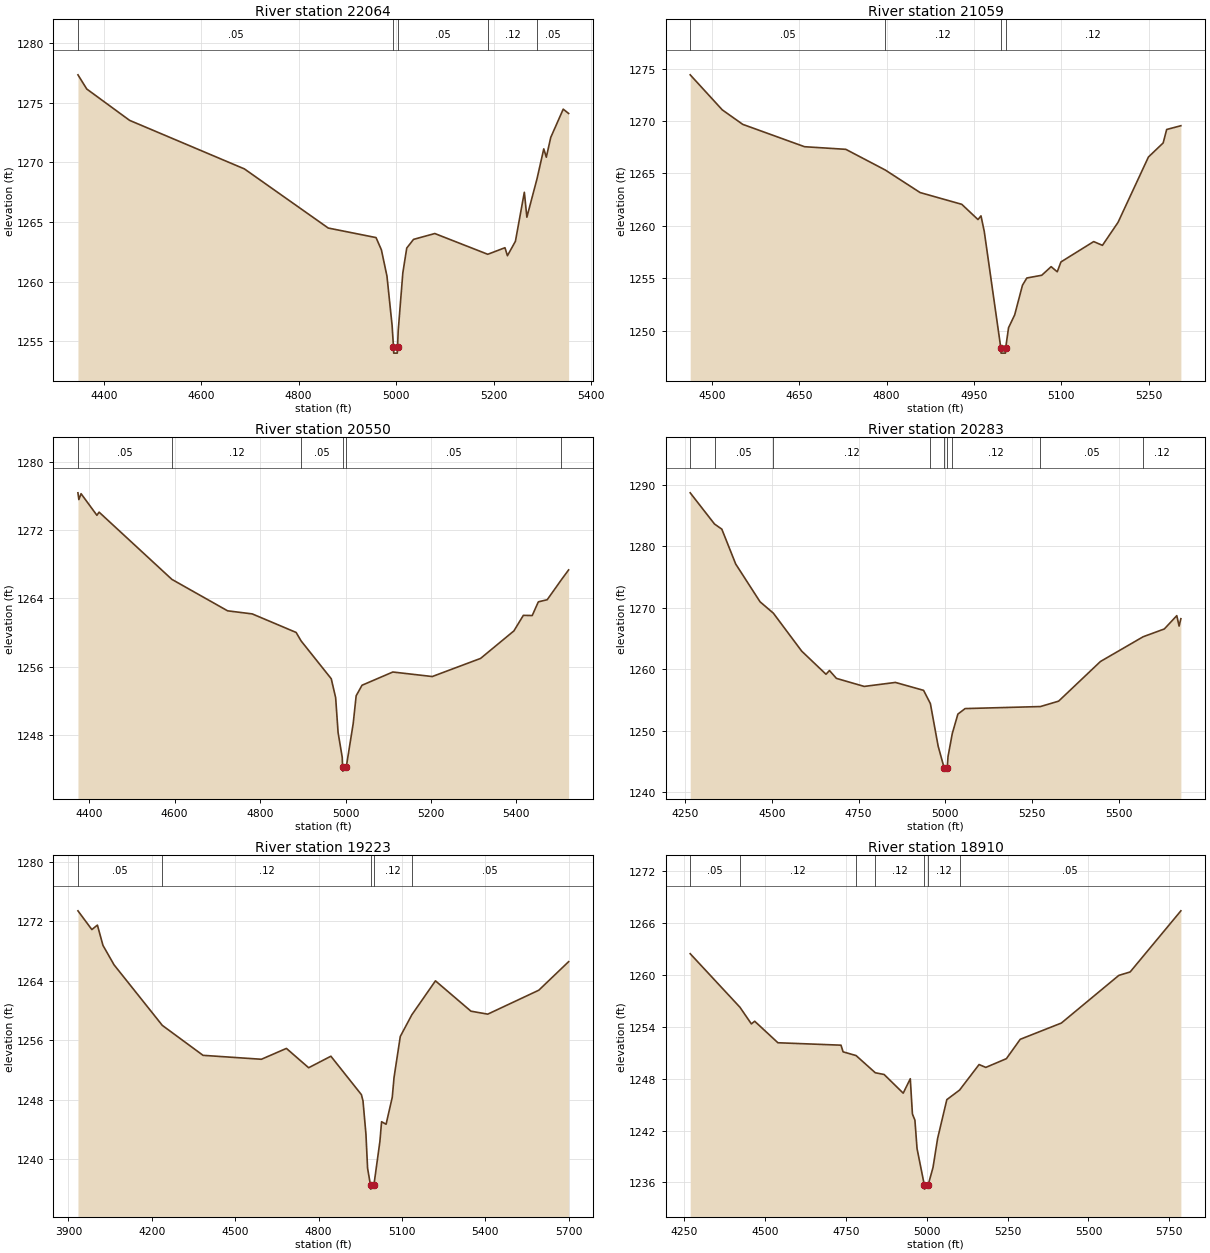
Type RM Length L Ch R = 1 ,22064   ,1005,1005,1005
BEGIN DESCRIPTION:
HONDO CREEK 43.0
END DESCRIPTION:
XS GIS Cut Line= 3
       2816262.1     10186789.99      2815605.89     10186489.66
      2815330.27     10186415.12
#Sta/Elev= 30
  4346.9 1277.34    4365 1276.15    4453 1273.52  4688.6 1269.45  4860.7 1264.49
  4958.8 1263.69  4969.8 1262.66  4981.2 1260.46  4991.8 1256.31  4994.6  1254.5
  4995.1    1254  5002.4    1254  5002.9  1254.5  5004.3 1255.88  5013.8 1260.74
  5021.8 1262.81  5035.8 1263.54  5079.4 1264.03  5188.1 1262.29  5223.4 1262.84
  5228.5 1262.17  5244.9 1263.38  5263.2 1267.49  5268.4  1265.4  5289.2 1268.62
  5303.1 1271.13  5308.3 1270.43  5317.4 1272.09    5343 1274.46  5354.1  1274.1
#Mann= 5 ,-1 , 0
  4346.9     .05       0  4994.6     .05       0  5002.9     .05       0
  5188.1     .12       0  5289.2     .05       0
Bank Sta=4994.6,5002.9
XS Rating Curve= 0 ,0
Exp/Cntr=0.3,0.1

Type RM Length L Ch R = 1 ,21059   ,509,509,509
BEGIN DESCRIPTION:
HONDO CREEK 42.0
END DESCRIPTION:
XS GIS Cut Line= 3
      2816348.94      10186227.5      2816017.35     10185921.95
      2815642.37     10185809.11
#Sta/Elev= 30
  4462.9  1274.4    4518 1271.06  4553.1 1269.68  4659.2 1267.55  4730.1  1267.3
  4797.8 1265.33  4857.7 1263.18  4929.2 1262.06    4957 1260.61  4962.2 1260.96
  4967.8 1259.48  4996.2 1248.38  4996.7 1247.88  5004.1 1247.88  5004.6 1248.38
  5009.5  1250.3    5020 1251.52  5033.4 1254.35  5040.9 1255.04  5066.5  1255.3
  5082.6 1256.12  5093.1 1255.63  5099.5 1256.57  5155.7 1258.51  5170.7 1258.15
  5197.5 1260.34  5249.7 1266.57    5275 1267.91    5281 1269.19  5305.4 1269.55
#Mann= 4 ,-1 , 0
  4462.9     .05       0  4797.8     .12       0  4996.2     .07       0
  5004.6     .12       0
Bank Sta=4996.2,5004.6
XS Rating Curve= 0 ,0
Exp/Cntr=0.3,0.1

Type RM Length L Ch R = 1 ,20550   ,267,267,267
BEGIN DESCRIPTION:
HONDO CREEK 41.0
END DESCRIPTION:
XS GIS Cut Line= 3
      2816732.65     10185588.62      2816036.45     10185423.69
      2815705.66     10185703.14
#Sta/Elev= 30
  4373.7 1276.34  4375.8 1275.55    4381 1276.24  4418.1 1273.71  4423.2 1274.08
  4593.6 1266.21    4724 1262.53  4781.7 1262.17  4884.4    1260    4896 1259.01
  4966.6 1254.58  4976.9 1252.36  4982.6 1248.29  4992.3 1245.38  4993.1 1244.27
  4993.6 1243.77  5001.8 1244.27    5018 1249.35  5024.9 1252.59  5038.6 1253.82
  5110.7 1255.37    5203 1254.84  5316.1 1256.96  5394.1 1260.18  5416.2    1262
    5437 1261.98  5451.3 1263.58  5472.1 1263.83  5505.4 1266.18  5522.2 1267.32
#Mann= 6 ,-1 , 0
  4373.7     .05       0  4593.6     .12       0    4896     .05       0
  4993.1     .05       0  5001.8     .05       0  5505.4     .12       0
Bank Sta=4993.1,5001.8
XS Rating Curve= 0 ,0
Exp/Cntr=0.3,0.1

Type RM Length L Ch R = 1 ,20283   ,1060,1060,1060
BEGIN DESCRIPTION:
HONDO CREEK 40.0
END DESCRIPTION:
XS GIS Cut Line= 3
      2816796.83     10185163.27      2816129.79     10185160.29
       2815634.6     10185718.84
#Sta/Elev= 30
  4264.8 1288.73  4334.8 1283.65  4355.9 1282.81  4395.9 1277.13    4466 1270.98
  4504.4 1269.12    4586 1262.94    4656 1259.17    4666 1259.78    4686  1258.5
    4766 1257.19    4856 1257.84  4937.1 1256.55  4956.7 1254.39  4979.1 1247.45
  4996.5 1243.89    4997 1243.39  5005.2 1243.89  5007.5 1245.76  5019.8 1249.52
  5035.9 1252.68  5056.8 1253.58  5273.7 1253.91  5326.1 1254.79  5446.6 1261.25
  5569.5 1265.28  5630.6 1266.55  5666.5 1268.72  5673.2 1267.02  5678.3 1268.22
#Mann= 9 ,-1 , 0
  4264.8     .12       0  4334.8     .05       0  4504.4     .12       0
  4956.7     .05       0  4996.5     .05       0  5005.2     .05       0
  5019.8     .12       0  5273.7     .05       0  5569.5     .12       0
Bank Sta=4996.5,5005.2
XS Rating Curve= 0 ,0
Exp/Cntr=0.3,0.1

Type RM Length L Ch R = 1 ,19223   ,313,313,313
BEGIN DESCRIPTION:
HONDO CREEK 39.0
END DESCRIPTION:
XS GIS Cut Line= 3
      2816805.65     10184803.11      2815824.64     10184816.05
      2815126.73     10184458.41
#Sta/Elev= 30
  3934.4 1273.43  3984.4 1270.91  4004.4 1271.51  4024.4 1268.78  4064.4 1266.16
  4237.9 1258.02  4384.4 1253.99  4594.4 1253.46  4684.4 1254.92  4764.4 1252.32
  4844.4 1253.87  4954.2  1248.7  4959.9 1247.86  4970.5  1243.4  4976.4 1238.81
    4987 1236.49  4987.5 1235.99    4999 1236.49  5020.8 1242.42  5026.7 1245.06
    5043 1244.72  5065.2 1248.35  5071.6 1251.01  5094.1 1256.53  5135.6 1259.44
  5220.6 1264.01  5348.2 1259.93  5408.7 1259.53  5592.4 1262.75  5699.7 1266.59
#Mann= 5 ,-1 , 0
  3934.4     .05       0  4237.9     .12       0    4987     .07       0
    4999     .12       0  5135.6     .05       0
Bank Sta=4987,4999
XS Rating Curve= 0 ,0
Exp/Cntr=0.3,0.1

Type RM Length L Ch R = 1 ,18910   ,717,717,717
BEGIN DESCRIPTION:
HONDO CREEK 38.0
END DESCRIPTION:
XS GIS Cut Line= 3
      2816639.98     10184754.86      2816023.64     10184612.49
      2815355.27     10184032.65
#Sta/Elev= 30
  4268.3 1262.46  4422.1 1256.27  4457.5 1254.34  4467.7 1254.65  4539.6 1252.16
  4734.6 1251.88  4741.1 1251.11  4781.2 1250.68  4840.7 1248.69    4868 1248.49
    4927 1246.33  4948.9    1248  4955.5 1243.92  4963.2 1243.21  4969.8 1239.92
  4992.2 1235.73  4992.7 1235.23  5004.3 1235.73  5019.2 1237.74  5033.4 1241.09
  5061.9 1245.58  5101.4 1246.69  5161.6 1249.64  5182.5 1249.31  5246.1 1250.32
  5288.9 1252.56  5416.1 1254.44  5593.7 1259.95  5628.8 1260.35  5785.7 1267.42
#Mann= 7 ,-1 , 0
  4268.3     .05       0  4422.1     .12       0  4781.2     .05       0
  4840.7     .12       0  4992.2     .07       0  5004.3     .12       0
  5101.4     .05       0
Bank Sta=4992.2,5004.3
XS Rating Curve= 0 ,0
Exp/Cntr=0.3,0.1

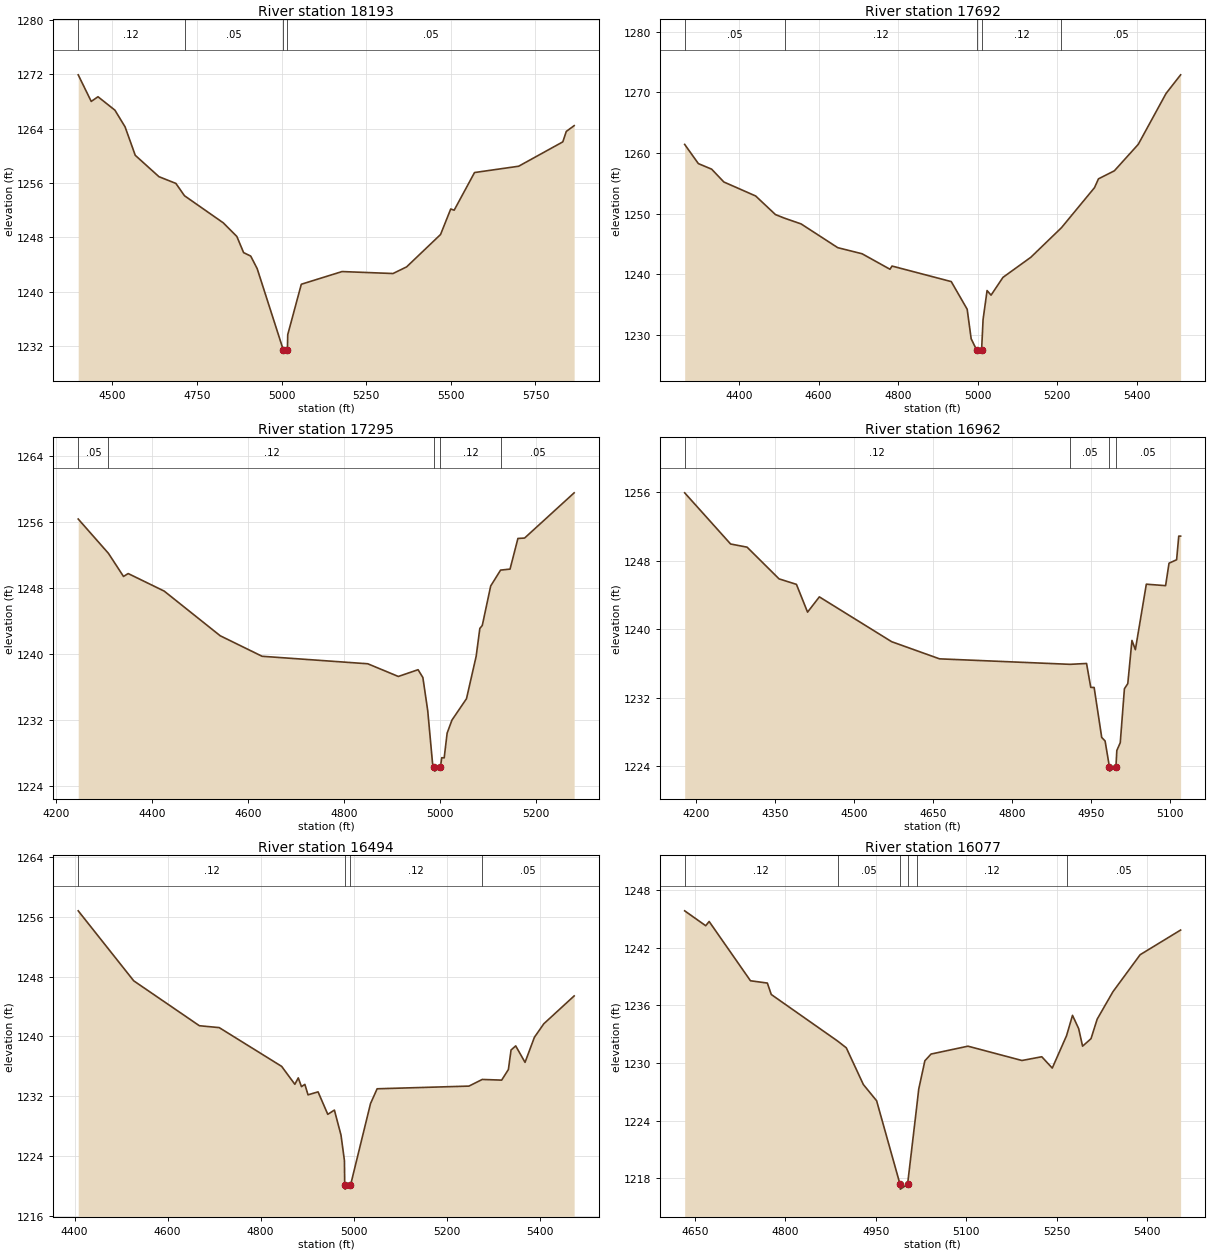
Type RM Length L Ch R = 1 ,18193   ,501,501,501
BEGIN DESCRIPTION:
HONDO CREEK 36.0
END DESCRIPTION:
XS GIS Cut Line= 3
      2816994.13     10184048.25      2816488.68     10184066.92
      2815532.31     10183985.75
#Sta/Elev= 30
  4398.7 1271.95  4437.2 1268.03  4457.2 1268.72  4507.2 1266.74  4537.2 1264.28
  4567.3 1260.09  4637.3 1256.94  4687.3 1255.95  4712.8 1254.13  4827.4 1250.14
  4867.5 1248.13  4887.5 1245.75  4908.5 1245.24  4927.6 1243.39  5004.6 1231.44
  5005.1 1230.94  5016.9 1231.44  5017.9 1233.66    5058 1241.09  5178.5 1242.96
    5329 1242.67  5369.2 1243.65  5469.5 1248.42  5499.6 1252.18  5509.7    1252
  5569.9 1257.55  5700.3 1258.48  5830.8 1262.07  5841.1 1263.61  5864.3 1264.46
#Mann= 4 ,-1 , 0
  4398.7     .12       0  4712.8     .05       0  5004.6     .05       0
  5016.9     .05       0
Bank Sta=5004.6,5016.9
XS Rating Curve= 0 ,0
Exp/Cntr=0.3,0.1

Type RM Length L Ch R = 1 ,17692   ,397,397,397
BEGIN DESCRIPTION:
HONDO CREEK 35.0
END DESCRIPTION:
XS GIS Cut Line= 3
      2816942.01     10183735.75      2816318.78     10183603.81
      2815709.22     10183603.81
#Sta/Elev= 30
  4263.5 1261.42  4297.9 1258.25  4331.3 1257.33    4362 1255.21  4441.9  1252.9
  4491.6 1249.83  4514.5 1249.23  4556.2 1248.28  4648.2 1244.36  4709.5 1243.35
  4779.6 1240.79  4784.7 1241.32  4933.6 1238.75  4973.6 1234.18  4983.6 1229.31
  4997.5 1227.43    4998 1226.93  5009.8 1227.43  5013.6 1232.51  5023.6 1237.27
  5033.6 1236.51  5063.6 1239.45  5133.6 1242.77  5210.5 1247.65  5293.6 1254.27
  5303.6 1255.73  5343.6 1257.06  5403.6 1261.43  5473.6 1269.85  5510.1 1272.92
#Mann= 5 ,-1 , 0
  4263.5     .05       0  4514.5     .12       0  4997.5     .07       0
  5009.8     .12       0  5210.5     .05       0
Bank Sta=4997.5,5009.8
XS Rating Curve= 0 ,0
Exp/Cntr=0.3,0.1

Type RM Length L Ch R = 1 ,17295   ,333,333,333
BEGIN DESCRIPTION:
HONDO CREEK 34.0
END DESCRIPTION:
XS GIS Cut Line= 3
      2816964.62     10183444.09      2816322.26     10183218.39
      2815973.33     10183173.26
#Sta/Elev= 30
  4246.4 1256.39  4309.4 1252.22  4340.7 1249.42  4350.5 1249.77  4425.5 1247.64
  4542.1 1242.22  4629.3 1239.73  4849.4 1238.82    4913 1237.28  4954.1  1238.1
  4964.1 1237.15  4974.2 1233.13  4984.3  1226.7  4988.2 1226.29  4988.7 1225.79
  5000.6 1226.29  5003.4 1227.42  5008.5  1227.4  5014.6  1230.4  5024.6 1231.98
  5054.9 1234.58  5075.1 1239.74  5082.7 1243.11  5087.8 1243.47  5105.3 1248.26
  5125.9 1250.19  5145.6 1250.31    5162 1254.03  5175.9 1254.08  5279.1 1259.57
#Mann= 5 ,-1 , 0
  4246.4     .05       0  4309.4     .12       0  4988.2     .07       0
  5000.6     .12       0  5125.9     .05       0
Bank Sta=4988.2,5000.6
XS Rating Curve= 0 ,0
Exp/Cntr=0.3,0.1

Type RM Length L Ch R = 1 ,16962   ,468,468,468
BEGIN DESCRIPTION:
HONDO CREEK 33.0
END DESCRIPTION:
XS GIS Cut Line= 3
      2817079.16      10183190.6      2816409.06     10182989.23
      2816256.26      10182801.7
#Sta/Elev= 30
  4177.9 1255.93  4265.1 1249.96  4296.4 1249.59  4357.1 1245.89  4390.1 1245.25
  4411.2 1242.01  4433.6 1243.79  4570.9 1238.56  4661.8 1236.56  4909.5 1235.92
  4940.9 1236.02  4948.9 1233.23  4955.3 1233.22  4969.7 1227.39  4976.1 1226.98
  4984.3 1223.96  4984.8 1223.46  4996.7 1223.96  4998.4 1225.87  5004.9 1226.78
  5012.8 1233.07  5019.2 1233.67  5027.1 1238.71  5033.6 1237.63  5054.4 1245.27
    5091  1245.1  5097.5 1247.72  5111.9 1248.12    5116 1250.88  5119.5 1250.88
#Mann= 4 ,-1 , 0
  4177.9     .12       0  4909.5     .05       0  4984.3     .05       0
  4996.7     .05       0
Bank Sta=4984.3,4996.7
XS Rating Curve= 0 ,0
Exp/Cntr=0.3,0.1

Type RM Length L Ch R = 1 ,16494   ,417,417,417
BEGIN DESCRIPTION:
HONDO CREEK 32.0
END DESCRIPTION:
XS GIS Cut Line= 3
      2817126.06     10183001.36      2816633.02     10182544.78
      2816240.71     10182503.12
#Sta/Elev= 30
  4407.9  1256.8  4527.3 1247.43  4668.5 1241.42  4711.1 1241.17  4845.4 1235.98
  4873.8 1233.58  4881.1 1234.44    4888 1233.27  4895.3 1233.57  4902.1 1232.17
  4923.7 1232.57  4944.6 1229.56  4958.8 1230.13    4973 1226.79  4980.4 1223.37
    4981 1220.05  4981.5 1219.55  4993.4 1220.05  5036.5    1231  5050.7 1232.98
  5248.2 1233.34  5276.8 1234.23  5318.5 1234.14    5333 1235.56  5338.7 1238.17
  5348.7 1238.72  5368.8 1236.52  5388.9 1239.87  5409.1 1241.68  5474.4 1245.41
#Mann= 4 ,-1 , 0
  4407.9     .12       0    4981     .07       0  4993.4     .12       0
  5276.8     .05       0
Bank Sta=4981,4993.4
XS Rating Curve= 0 ,0
Exp/Cntr=0.3,0.1

Type RM Length L Ch R = 1 ,16077   ,236,236,236
BEGIN DESCRIPTION:
HONDO CREEK 31.0
END DESCRIPTION:
XS GIS Cut Line= 3
      2817030.56      10182315.6      2816829.58     10182201.22
      2816250.01     10182320.69
#Sta/Elev= 30
  4632.9 1245.84  4667.8 1244.29  4673.5 1244.73  4742.1 1238.56  4770.1 1238.32
  4776.6 1237.13  4886.8 1232.28  4901.1 1231.58  4929.4 1227.76  4951.4 1226.07
  4990.3 1217.37  4990.8 1216.87  5002.8 1217.37  5017.8 1225.36  5021.3 1227.28
  5031.5 1230.23  5041.7 1230.93    5103 1231.75  5192.6 1230.26  5225.5 1230.65
  5242.9 1229.47  5266.6 1232.84  5276.5 1234.96  5286.7 1233.58  5293.2 1231.75
  5307.2 1232.53  5317.4 1234.56  5343.5 1237.41  5388.7 1241.27  5455.9 1243.84
#Mann= 6 ,-1 , 0
  4632.9     .12       0  4886.8     .05       0  4990.3     .05       0
  5002.8     .05       0  5017.8     .12       0  5266.6     .05       0
Bank Sta=4990.3,5002.8
XS Rating Curve= 0 ,0
Exp/Cntr=0.3,0.1

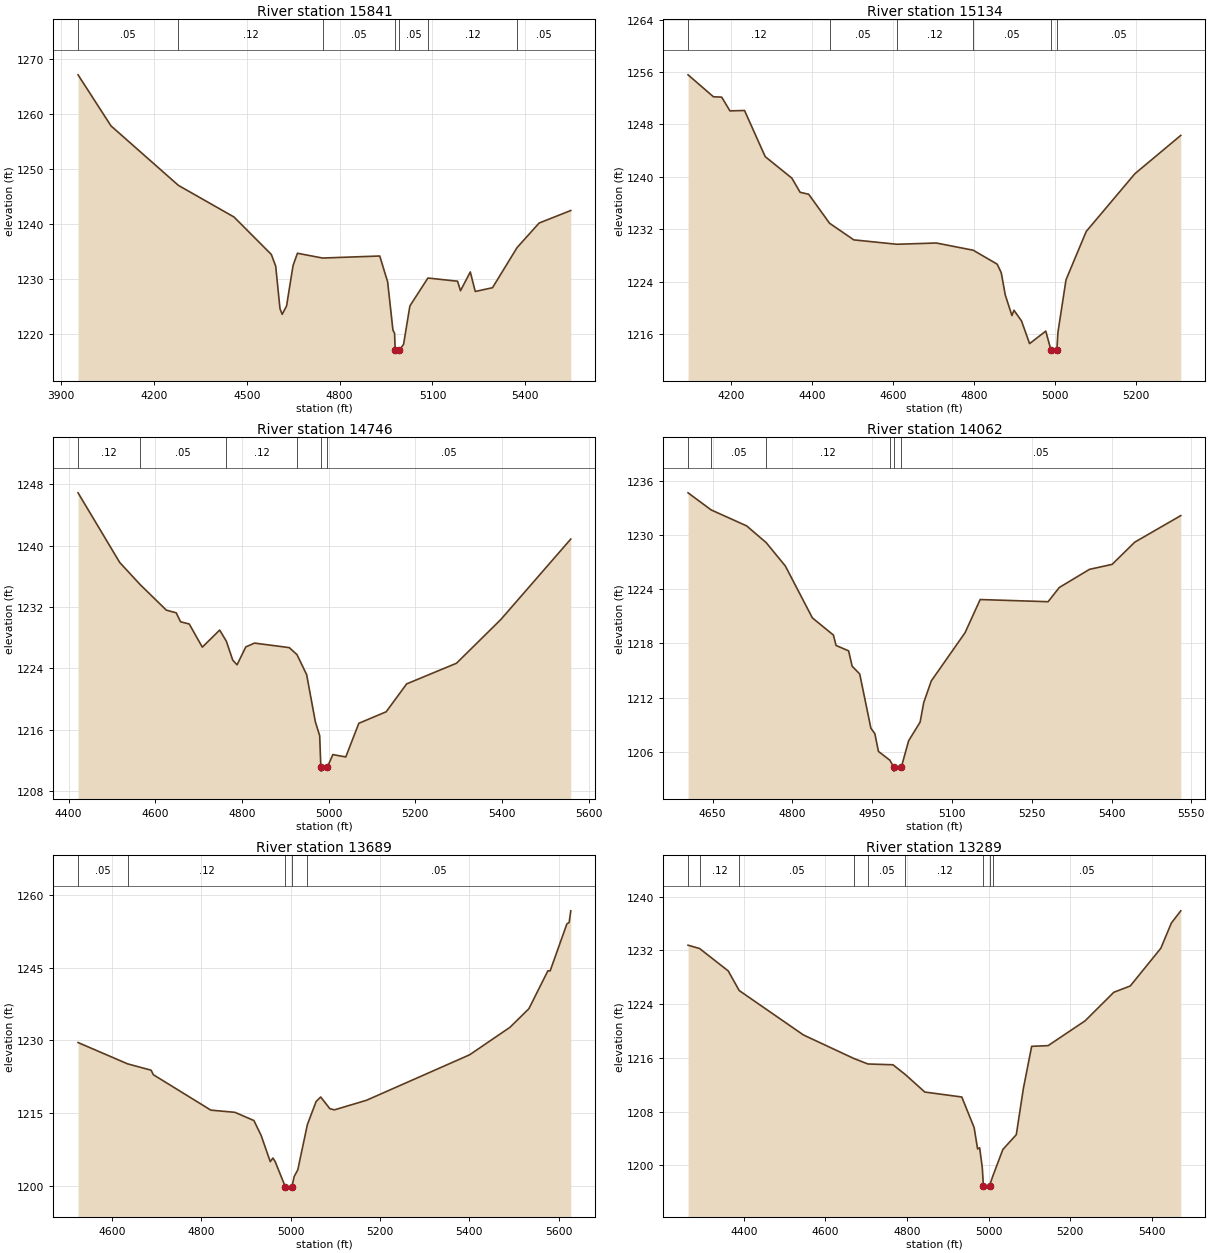
Type RM Length L Ch R = 1 ,15841   ,707,707,707
BEGIN DESCRIPTION:
Mapping XS afaf4cbe
END DESCRIPTION:
XS GIS Cut Line= 4
      2817468.07     10181334.74      2816931.63     10181940.61
      2816378.29     10182069.26      2816261.18     10182248.82
#Sta/Elev= 30
  3955.1 1267.13  4061.6 1257.83  4279.2 1247.01  4458.9 1241.25  4579.4 1234.44
  4593.6 1232.31  4607.4 1224.59  4614.5 1223.53  4628.7 1225.06  4649.6  1232.4
  4663.8 1234.65    4745 1233.78  4929.7 1234.15  4955.2 1229.45  4972.4 1220.63
  4977.5 1220.12  4979.8 1216.97  4980.3 1216.47  4992.3 1216.97  5006.6 1218.06
  5027.1 1225.06  5085.3 1230.14  5181.1 1229.56  5190.6 1227.83  5222.2 1231.25
  5238.3 1227.69    5294 1228.38  5373.3 1235.68  5444.5 1240.15  5546.8 1242.43
#Mann= 7 ,-1 , 0
  3955.1     .05       0  4279.2     .12       0    4745     .05       0
  4979.8     .05       0  4992.3     .05       0  5085.3     .12       0
  5373.3     .05       0
Bank Sta=4979.8,4992.3
XS Rating Curve= 0 ,0
Exp/Cntr=0.3,0.1

Type RM Length L Ch R = 1 ,15134   ,388,388,388
BEGIN DESCRIPTION:
HONDO CREEK 30.0
END DESCRIPTION:
XS GIS Cut Line= 3
      2817237.18     10181320.83      2816617.39     10181444.09
      2816032.28     10181457.98
#Sta/Elev= 30
  4094.3 1255.56    4157 1252.21  4177.4 1252.16  4197.8 1250.06  4233.8 1250.12
  4284.9 1243.08  4350.7  1239.8  4371.1 1237.64  4392.3 1237.34  4443.8 1232.92
  4503.7 1230.38  4609.9 1229.71  4707.6  1229.9  4798.8  1228.8    4858 1226.67
    4868 1225.37    4878 1221.96  4894.4 1218.83  4899.4 1219.64    4918 1218.02
    4938 1214.55    4978 1216.46  4990.6  1213.6  4991.1  1213.1  5005.4  1213.6
    5008 1216.26    5028 1224.29    5078 1231.67  5198.1 1240.47  5311.5 1246.32
#Mann= 6 ,-1 , 0
  4094.3     .12       0  4443.8     .05       0  4609.9     .12       0
  4798.8     .05       0  4990.6     .03       0  5005.4     .05       0
Bank Sta=4990.6,5005.4
XS Rating Curve= 0 ,0
Exp/Cntr=0.3,0.1

Type RM Length L Ch R = 1 ,14746   ,684,684,684
BEGIN DESCRIPTION:
HONDO CREEK 29.0
END DESCRIPTION:
XS GIS Cut Line= 3
      2817051.46     10181051.72      2816181.16     10181121.18
      2816055.67     10181353.14
#Sta/Elev= 30
  4421.8 1246.88  4517.9  1237.8  4565.3  1234.9  4625.5 1231.58  4648.3 1231.23
  4658.3 1230.06  4678.4 1229.77  4708.5 1226.75  4748.6 1228.98    4764 1227.52
  4778.7 1225.06  4788.7 1224.45  4808.8 1226.78  4828.9 1227.28  4909.1 1226.69
  4926.9 1225.78  4949.2 1223.17  4969.3 1217.02  4979.3  1215.2    4982 1211.08
  4982.5 1210.58  4996.8 1211.08  5009.7 1212.74  5039.5 1212.43  5069.6 1216.82
  5132.7 1218.32    5180 1221.96  5294.9 1224.65  5397.3 1230.36  5558.6 1240.85
#Mann= 6 ,-1 , 0
  4421.8     .12       0  4565.3     .05       0    4764     .12       0
  4926.9     .05       0    4982     .05       0  4996.8     .05       0
Bank Sta=4982,4996.8
XS Rating Curve= 0 ,0
Exp/Cntr=0.3,0.1

Type RM Length L Ch R = 1 ,14062   ,373,373,373
BEGIN DESCRIPTION:
HONDO CREEK 28.0
END DESCRIPTION:
XS GIS Cut Line= 3
      2816481.97     10180464.92      2816211.14     10180539.57
      2815733.68     10180973.63
#Sta/Elev= 30
  4603.9 1234.66  4647.3 1232.77  4714.1    1231  4750.9 1229.14  4786.8 1226.56
  4837.6 1220.82  4877.1 1218.92  4882.1 1217.77  4905.7 1217.17  4912.4 1215.47
  4926.6 1214.61  4947.6 1208.61    4955 1208.01  4961.8 1206.04  4983.2 1205.07
  4990.1 1204.36  4990.6 1203.86  5005.1 1204.36  5018.5 1207.22  5040.1 1209.28
  5046.9 1211.45  5061.1 1213.84  5124.6 1219.18    5153 1222.85  5280.7 1222.61
  5301.7 1224.18  5358.4 1226.19    5401 1226.74  5443.6  1229.2  5530.1 1232.14
#Mann= 6 ,-1 , 0
  4603.9     .12       0  4647.3     .05       0  4750.9     .12       0
  4983.2     .05       0  4990.1     .05       0  5005.1     .05       0
Bank Sta=4990.1,5005.1
XS Rating Curve= 0 ,0
Exp/Cntr=0.3,0.1

Type RM Length L Ch R = 1 ,13689   ,400,400,400
BEGIN DESCRIPTION:
HONDO CREEK 27.0
END DESCRIPTION:
XS GIS Cut Line= 3
      2816459.37     10180294.78      2816138.23      10180242.7
      2815380.14     10180419.64
#Sta/Elev= 30
  4523.5 1229.57  4634.3 1225.18  4687.2 1223.86  4692.2 1222.93    4821 1215.62
  4874.9 1215.17  4917.4 1213.48  4933.6 1210.41  4954.1 1204.99    4960 1205.73
  4965.1 1205.01  4987.7 1199.82  4988.2 1199.32  5002.7 1199.82  5007.6 1201.91
  5015.8 1203.31  5037.2 1212.63  5056.8  1217.4  5067.1 1218.33  5087.6 1215.92
  5097.9 1215.68  5169.8 1217.66  5400.7 1227.04  5490.9  1232.7  5533.4 1236.54
    5576 1244.37  5581.1 1244.36  5618.5 1254.03  5623.7 1254.36  5627.3 1256.75
#Mann= 5 ,-1 , 0
  4523.5     .05       0  4634.3     .12       0  4987.7     .07       0
  5002.7     .12       0  5037.2     .05       0
Bank Sta=4987.7,5002.7
XS Rating Curve= 0 ,0
Exp/Cntr=0.3,0.1

Type RM Length L Ch R = 1 ,13289   ,508,508,508
BEGIN DESCRIPTION:
HONDO CREEK 26.0
END DESCRIPTION:
XS GIS Cut Line= 3
      2816572.27     10180214.93      2816162.53     10179859.02
      2815502.77     10179933.67
#Sta/Elev= 30
  4263.7 1232.78  4291.9 1232.29  4362.1 1228.95  4388.9 1226.03  4546.3 1219.41
    4670  1215.9  4704.3 1215.09  4765.6 1214.97  4796.1  1213.5  4843.5 1210.91
  4934.1 1210.17  4964.3 1205.62  4972.8 1202.43  4977.8 1202.62  4984.4 1199.59
  4986.9 1196.95  4987.4 1196.45    5002 1196.95  5010.3 1198.43  5034.7 1202.36
  5067.6 1204.56    5085 1211.47  5105.2 1217.72  5145.4 1217.82    5236 1221.51
  5306.4 1225.77  5346.7 1226.71  5421.5 1232.32  5447.3 1236.08  5470.4  1237.9
#Mann= 9 ,-1 , 0
  4263.7     .05       0  4291.9     .12       0  4388.9     .05       0
    4670     .12       0  4704.3     .05       0  4796.1     .12       0
  4986.9     .07       0    5002     .12       0  5010.3     .05       0
Bank Sta=4986.9,5002
XS Rating Curve= 0 ,0
Exp/Cntr=0.3,0.1