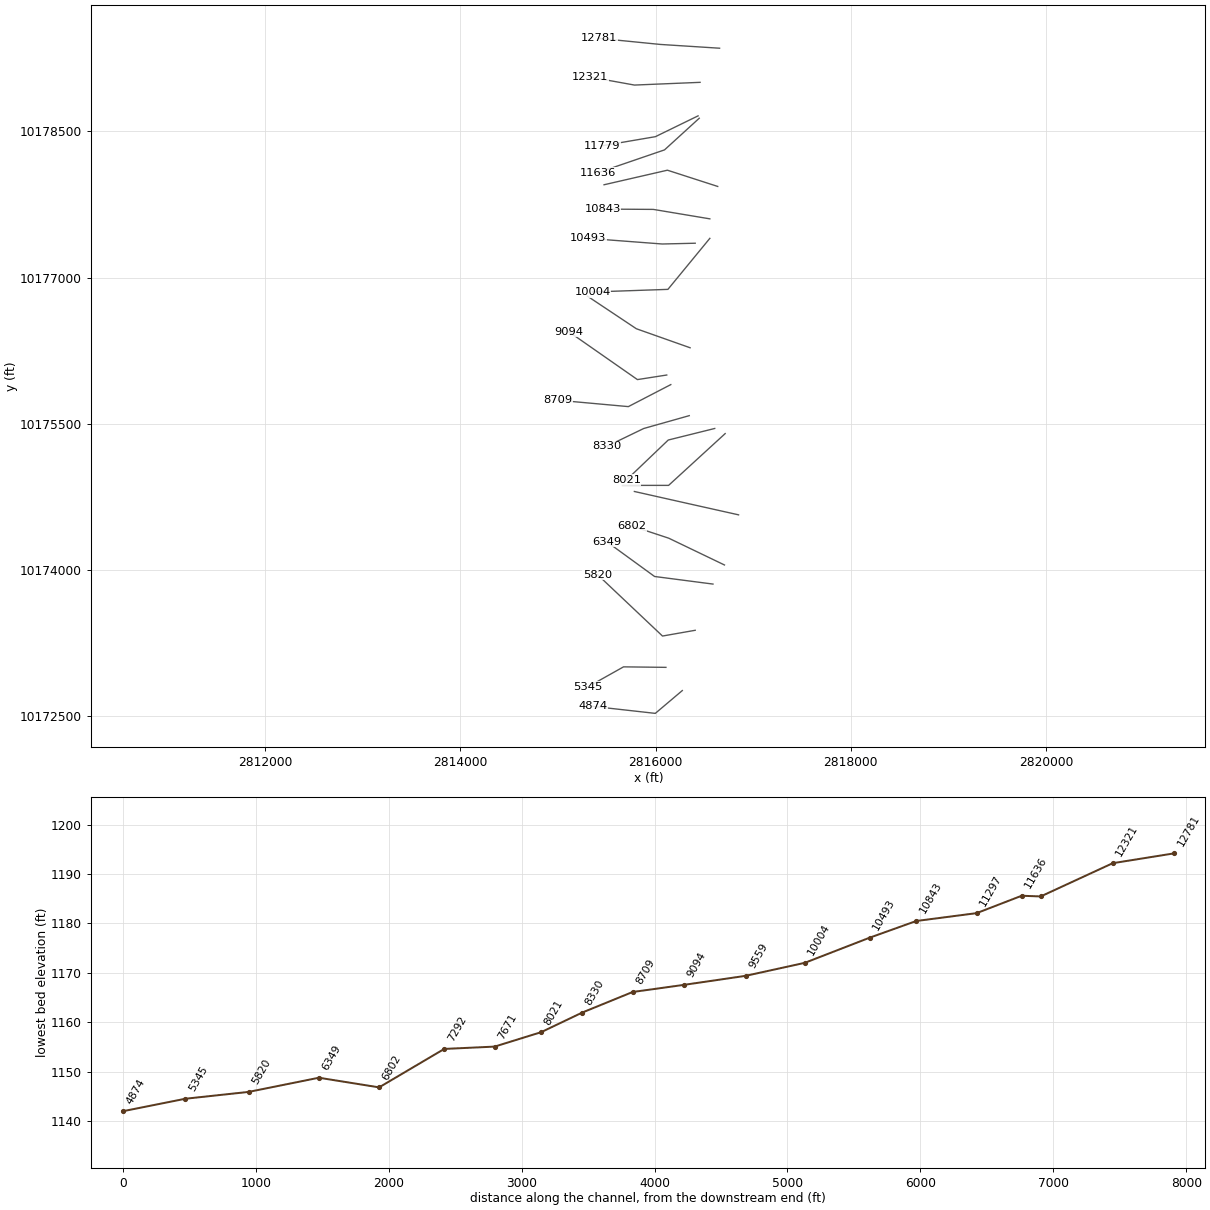
HEC-RAS study HONDO CREEK.prj: HONDO CREEK Base Level Engineering

--- HONDO CREEK.g01 (geometry) --- (continued)

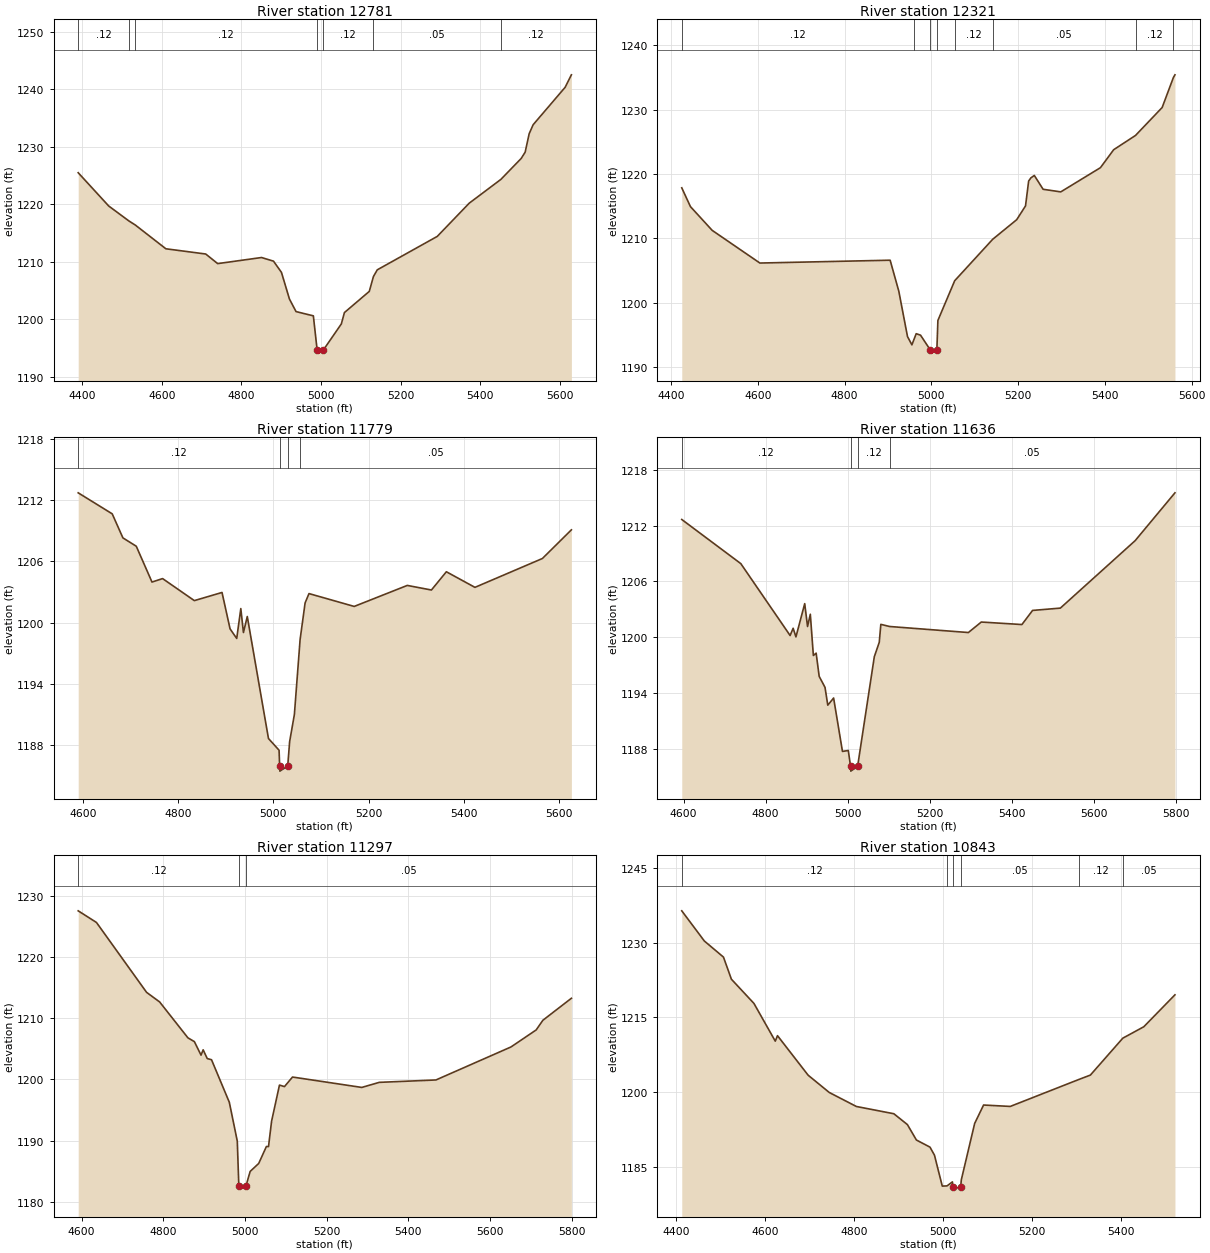
Type RM Length L Ch R = 1 ,12781   ,460,460,460
BEGIN DESCRIPTION:
HONDO CREEK 25.0
END DESCRIPTION:
XS GIS Cut Line= 3
      2816655.66     10179353.11       2816046.5       10179392.
       2815420.1     10179454.44
#Sta/Elev= 30
  4389.6 1225.51  4466.4 1219.72  4517.1 1217.13    4533 1216.43    4610 1212.29
  4710.2 1211.38  4740.3 1209.71  4850.5 1210.77  4880.6 1210.14  4900.6 1208.19
  4920.7 1203.55  4937.3 1201.37  4980.8 1200.63  4990.4 1194.65  4990.9 1194.15
  5005.5 1194.65  5051.1 1199.22  5058.9  1201.2  5121.4 1204.88  5131.8 1207.46
  5141.5 1208.63  5292.3 1214.44  5372.7 1220.22  5452.2 1224.35  5503.3 1227.99
  5513.3 1229.09  5523.4  1232.3  5533.4 1233.86  5613.8 1240.36  5629.5 1242.53
#Mann= 7 ,-1 , 0
  4389.6     .12       0  4517.1     .05       0    4533     .12       0
  4990.4     .07       0  5005.5     .12       0  5131.8     .05       0
  5452.2     .12       0
Bank Sta=4990.4,5005.5
XS Rating Curve= 0 ,0
Exp/Cntr=0.3,0.1

Type RM Length L Ch R = 1 ,12321   ,542,542,542
BEGIN DESCRIPTION:
HONDO CREEK 24.0
END DESCRIPTION:
XS GIS Cut Line= 3
      2816455.68     10179003.11      2815783.22     10178975.19
      2815326.67     10179057.76
#Sta/Elev= 30
  4424.5 1217.86  4444.5 1214.94  4494.6 1211.25  4604.6 1206.17  4904.9 1206.61
  4924.9 1201.79  4944.9 1194.75    4955 1193.46  4959.8 1194.29    4965 1195.19
    4975 1194.96  4997.4 1192.67  4997.9 1192.17  5012.6 1192.67    5015 1197.25
  5053.7 1203.42  5141.3 1209.86  5196.7 1212.91    5217 1215.05  5224.2 1218.91
  5229.3  1219.4  5237.3 1219.78  5257.6 1217.63  5298.3 1217.23  5389.7 1220.99
  5420.2 1223.78  5470.6    1226    5532 1230.34  5557.9    1235  5561.5 1235.42
#Mann= 8 ,-1 , 0
  4424.5     .12       0  4959.8     .05       0  4997.4     .03       0
  5012.6     .05       0  5053.7     .12       0  5141.3     .05       0
  5470.6     .12       0  5557.9     .05       0
Bank Sta=4997.4,5012.6
XS Rating Curve= 0 ,0
Exp/Cntr=0.3,0.1

Type RM Length L Ch R = 1 ,11779   ,143,143,143
BEGIN DESCRIPTION:
HONDO CREEK 23.0
END DESCRIPTION:
XS GIS Cut Line= 3
      2816435.09     10178659.36       2815997.6     10178445.82
       2815455.7     10178353.11
#Sta/Elev= 30
  4589.8 1212.73  4661.3 1210.67  4683.8 1208.31  4711.9 1207.49  4744.9 1203.98
  4767.2 1204.32  4833.9 1202.16  4892.1 1202.96    4909 1199.39    4923 1198.45
  4931.6 1201.38  4937.1 1199.03  4945.2  1200.6  4989.7 1188.64    5012 1187.49
  5013.2 1185.94  5013.7 1185.44  5030.2 1185.94  5034.2 1188.33  5044.2    1191
  5056.2 1198.34  5066.7 1201.93  5074.9 1202.85  5169.9 1201.59  5281.5 1203.65
  5332.2  1203.2  5363.6 1204.99  5423.7 1203.46  5565.5 1206.29  5626.4  1209.1
#Mann= 4 ,-1 , 0
  4589.8     .12       0  5013.2     .07       0  5030.2     .12       0
  5056.2     .05       0
Bank Sta=5013.2,5030.2
XS Rating Curve= 0 ,0
Exp/Cntr=0.3,0.1

Type RM Length L Ch R = 1 ,11636   ,339,339,339
BEGIN DESCRIPTION:
HONDO CREEK 22.0
END DESCRIPTION:
XS GIS Cut Line= 3
      2816447.24     10178635.04      2816091.35     10178310.41
        2815409.     10178076.61
#Sta/Elev= 30
  4595.5 1212.67  4739.5 1207.92  4859.8 1200.18  4867.2 1200.96    4874 1200.03
  4895.4 1203.61  4902.3 1201.15  4909.1 1202.47  4916.5 1198.03  4923.3 1198.28
  4930.7 1195.78  4944.9  1194.6  4951.7 1192.68  4965.9 1193.45  4987.5  1187.7
  5001.7  1187.8  5007.3 1186.08  5007.8 1185.58  5024.4 1186.08  5065.2  1197.9
  5077.2 1199.44  5081.1 1201.38  5102.5 1201.15  5294.6  1200.5  5326.1 1201.63
  5425.2 1201.36  5451.2 1202.88    5519 1203.13  5701.4 1210.39  5798.5 1215.54
#Mann= 4 ,-1 , 0
  4595.5     .12       0  5007.3     .07       0  5024.4     .12       0
  5102.5     .05       0
Bank Sta=5007.3,5024.4
XS Rating Curve= 0 ,0
Exp/Cntr=0.3,0.1

Type RM Length L Ch R = 1 ,11297   ,454,454,454
BEGIN DESCRIPTION:
HONDO CREEK 21.0
END DESCRIPTION:
XS GIS Cut Line= 3
      2816636.46     10177935.42      2816120.87     10178102.07
      2815471.57     10177952.77
#Sta/Elev= 30
  4591.5 1227.57  4636.2 1225.67    4759 1214.24    4791 1212.67  4860.3  1206.8
  4876.1 1206.18  4892.4 1203.97  4897.6 1204.84  4907.6 1203.41  4918.1 1203.22
  4961.7 1196.26  4981.2 1189.91    4985 1182.56  4985.5 1182.06  5002.4 1182.56
  5012.7 1184.95  5033.7 1186.26  5052.5 1189.03  5057.7 1189.02  5065.2 1193.16
  5084.5 1199.07  5096.8 1198.83  5116.5 1200.39  5286.2 1198.69    5329 1199.52
  5467.8 1199.91  5651.7 1205.31  5713.3 1208.09  5729.9 1209.68  5799.6 1213.27
#Mann= 3 ,-1 , 0
  4591.5     .12       0    4985     .05       0  5002.4     .05       0
Bank Sta=4985,5002.4
XS Rating Curve= 0 ,0
Exp/Cntr=0.3,0.1

Type RM Length L Ch R = 1 ,10843   ,350,350,350
BEGIN DESCRIPTION:
HONDO CREEK 20.0
END DESCRIPTION:
XS GIS Cut Line= 3
      2816555.71     10177603.11      2815976.25       10177700.
      2815455.66     10177703.11
#Sta/Elev= 30
  4412.5  1236.4  4463.2 1230.34  4506.2  1227.1    4524 1222.66  4574.7 1217.79
  4622.6 1210.21  4627.6 1211.31  4696.4 1203.37    4744 1199.89  4804.8 1197.08
    4889 1195.62  4919.5 1193.44  4939.7 1190.34  4970.2 1188.91  4980.3 1187.29
  4997.8 1181.08  5008.5 1181.12  5020.6 1181.92  5021.9 1180.97  5022.4 1180.47
  5039.3 1180.97  5040.6 1182.34  5070.6 1193.67  5090.6 1197.37  5150.6 1197.09
  5304.8 1202.51  5330.6 1203.39  5403.5 1210.81  5450.6  1213.1  5520.6 1219.52
#Mann= 6 ,-1 , 0
  4412.5     .12       0  5008.5     .05       0  5021.9     .07       0
  5039.3     .05       0  5304.8     .12       0  5403.5     .05       0
Bank Sta=5021.9,5039.3
XS Rating Curve= 0 ,0
Exp/Cntr=0.3,0.1

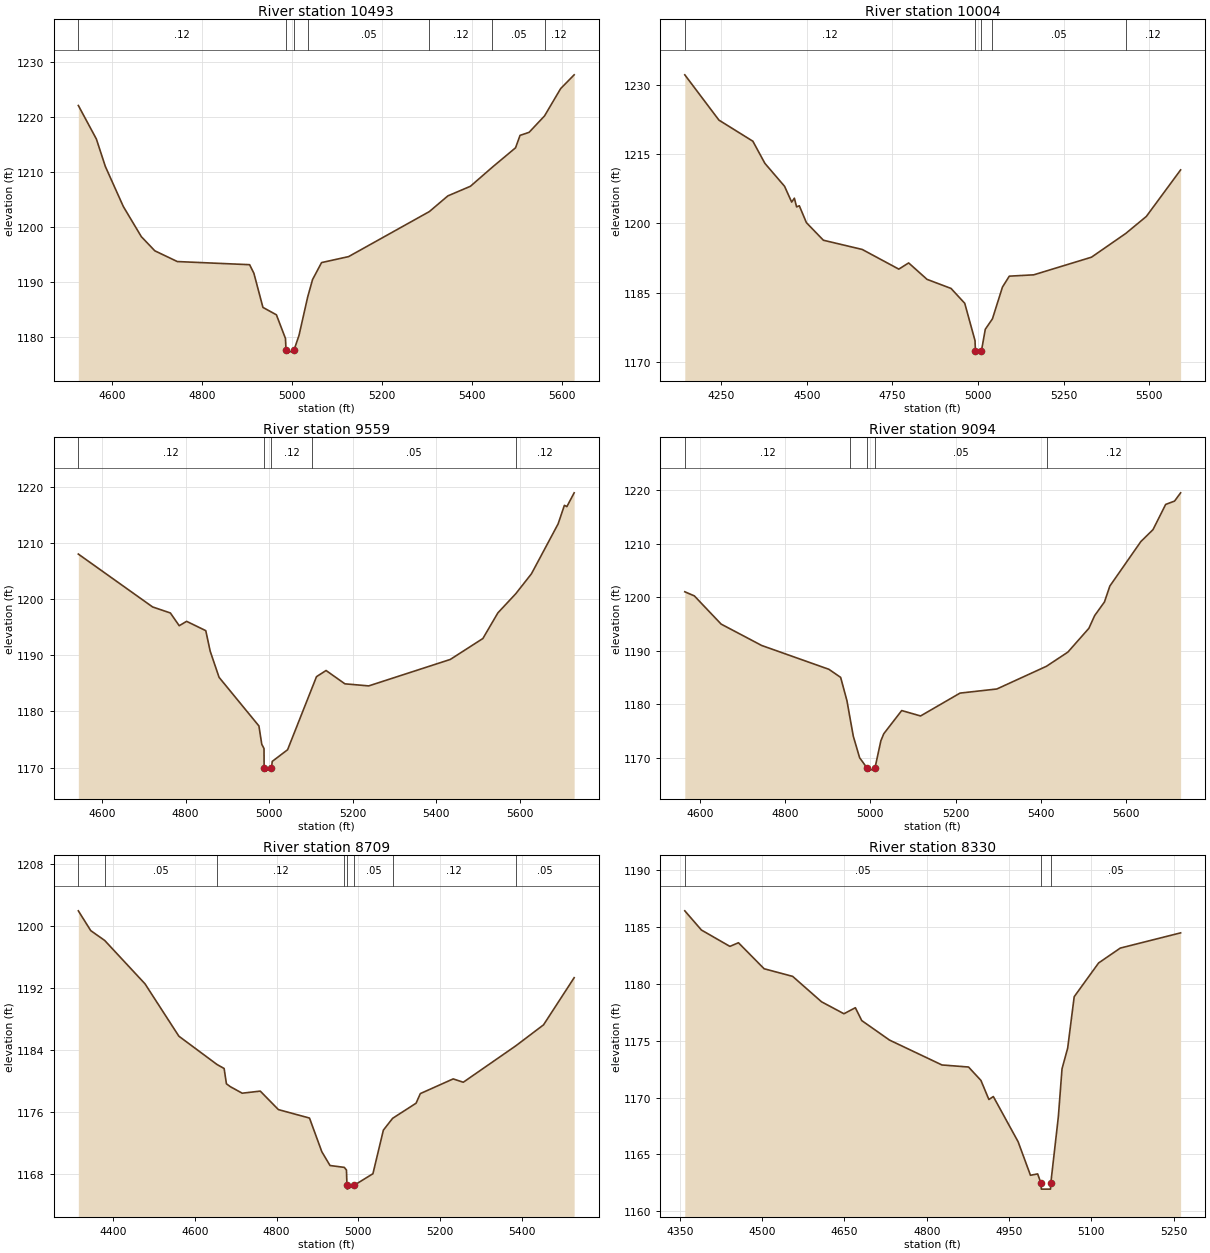
Type RM Length L Ch R = 1 ,10493   ,489,489,489
BEGIN DESCRIPTION:
HONDO CREEK 19.0
END DESCRIPTION:
XS GIS Cut Line= 3
      2816405.73     10177353.11      2816068.78     10177345.13
      2815305.73     10177403.11
#Sta/Elev= 30
  4524.7  1222.1  4564.8 1216.01  4584.8 1211.01  4624.8 1203.73  4664.8 1198.26
  4694.8 1195.69  4744.8 1193.74  4905.5 1193.17    4915 1191.61  4935.1 1185.41
  4965.1 1184.06  4985.2 1179.76  4986.5  1177.6    4987  1177.1    5004  1177.6
  5015.3 1180.33  5034.5 1187.27  5045.4 1190.46  5065.4 1193.55  5125.6 1194.64
  5305.1 1202.82  5346.2 1205.67  5396.4 1207.42  5444.6 1210.85  5496.7 1214.41
  5506.7 1216.67  5526.8 1217.22  5561.1  1220.2    5597 1225.17    5627 1227.67
#Mann= 7 ,-1 , 0
  4524.7     .12       0  4986.5     .07       0    5004     .12       0
  5034.5     .05       0  5305.1     .12       0  5444.6     .05       0
  5561.1     .12       0
Bank Sta=4986.5,5004
XS Rating Curve= 0 ,0
Exp/Cntr=0.3,0.1

Type RM Length L Ch R = 1 ,10004   ,445,445,445
BEGIN DESCRIPTION:
HONDO CREEK 18.0
END DESCRIPTION:
XS GIS Cut Line= 3
      2816555.68      10177403.1      2816126.08     10176879.85
      2815355.66     10176853.11
#Sta/Elev= 30
  4143.7  1232.1  4243.4 1222.32  4342.5 1217.76  4377.6 1212.98    4435 1208.03
  4455.8 1204.62  4463.7 1205.46  4470.2 1203.58  4478.1 1203.82  4498.9 1200.17
  4548.4 1196.38  4661.8 1194.39  4768.7 1190.14  4797.4 1191.48  4851.1 1187.93
  4921.2 1185.97  4961.2 1182.76  4991.2  1174.7  4992.4  1172.5  4992.9    1172
    5010  1172.5  5021.2 1177.15  5042.1 1179.41  5071.3 1186.26  5091.3 1188.62
  5162.7 1188.91  5331.4 1192.72  5431.3 1197.84  5491.5 1201.52  5591.6 1211.57
#Mann= 5 ,-1 , 0
  4143.7     .12       0  4992.4     .07       0    5010     .12       0
  5042.1     .05       0  5431.3     .12       0
Bank Sta=4992.4,5010
XS Rating Curve= 0 ,0
Exp/Cntr=0.3,0.1

Type RM Length L Ch R = 1 ,9559    ,465,465,465
BEGIN DESCRIPTION:
HONDO CREEK 17.0
END DESCRIPTION:
XS GIS Cut Line= 3
      2816353.51     10176280.89      2815802.47     10176476.04
      2815300.58     10176810.69
#Sta/Elev= 30
    4543 1208.03    4721 1198.61  4763.5 1197.54  4784.7 1195.27  4802.4 1196.05
  4848.3 1194.39  4858.9 1190.73  4880.2 1186.07  4975.6 1177.42  4982.5 1174.14
  4987.8  1173.4  4988.1 1169.87  4988.6 1169.37  5005.7 1169.87  5007.5  1171.1
  5044.3 1173.18  5103.9 1184.38  5113.6  1186.2  5136.5 1187.29  5181.6 1184.92
  5238.7 1184.55    5434 1189.26  5512.1 1192.99  5548.1 1197.56  5590.6 1200.94
  5628.5 1204.52  5692.4 1213.41  5707.4 1216.71  5713.4 1216.49  5730.8 1218.94
#Mann= 5 ,-1 , 0
    4543     .12       0  4988.1     .07       0  5005.7     .12       0
  5103.9     .05       0  5590.6     .12       0
Bank Sta=4988.1,5005.7
XS Rating Curve= 0 ,0
Exp/Cntr=0.3,0.1

Type RM Length L Ch R = 1 ,9094    ,385,385,385
BEGIN DESCRIPTION:
HONDO CREEK 16.0
END DESCRIPTION:
XS GIS Cut Line= 3
      2816113.94     10176001.38      2815813.58      10175954.5
      2815109.21     10176446.36
#Sta/Elev= 30
  4564.8 1201.06  4587.2 1200.29    4650 1195.02  4745.2 1191.02  4902.8 1186.57
  4930.4 1185.06  4945.2 1180.69  4952.5 1177.42  4960.1 1174.06  4974.9 1170.04
  4993.1 1168.04  4993.6 1167.54  5010.7 1168.04  5024.8 1173.23  5031.6 1174.53
  5073.6 1178.86  5117.9 1177.85  5210.4 1182.12  5296.8 1182.89  5413.3 1187.14
  5463.4 1189.78  5512.7 1194.23  5526.2  1196.6  5549.2 1199.15  5561.9 1202.13
  5634.6 1210.44  5663.1 1212.67  5692.8 1217.38  5713.7 1218.01  5727.9 1219.55
#Mann= 5 ,-1 , 0
  4564.8     .12       0  4952.5     .05       0  4993.1     .03       0
  5010.7     .05       0  5413.3     .12       0
Bank Sta=4993.1,5010.7
XS Rating Curve= 0 ,0
Exp/Cntr=0.3,0.1

Type RM Length L Ch R = 1 ,8709    ,379,379,379
BEGIN DESCRIPTION:
HONDO CREEK 15.0
END DESCRIPTION:
XS GIS Cut Line= 3
      2816155.68     10175903.11      2815720.55     10175677.31
      2815001.04      10175742.7
#Sta/Elev= 30
  4315.1 1201.93  4345.5 1199.38  4379.5 1198.12  4478.2 1192.53    4561 1185.79
  4654.2 1182.15  4671.7 1181.63  4677.3 1179.66  4686.9 1179.29  4715.9 1178.45
  4760.1 1178.72  4804.4 1176.34  4880.5 1175.25  4910.6 1170.92  4930.7 1169.14
  4965.6  1168.9  4970.9 1168.56  4972.1  1166.6  4972.6  1166.1  4989.8  1166.6
  5035.6 1168.08  5061.2  1173.7  5083.9 1175.22  5141.1 1177.16  5151.6  1178.4
  5231.9 1180.29  5256.6 1179.86  5385.1 1184.55  5452.9 1187.25  5527.8 1193.32
#Mann= 8 ,-1 , 0
  4315.1     .12       0  4379.5     .05       0  4654.2     .12       0
  4965.6     .05       0  4972.1     .03       0  4989.8     .05       0
  5083.9     .12       0  5385.1     .05       0
Bank Sta=4972.1,4989.8
XS Rating Curve= 0 ,0
Exp/Cntr=0.3,0.1

Type RM Length L Ch R = 1 ,8330    ,309,309,309
BEGIN DESCRIPTION:
HONDO CREEK 14.0
END DESCRIPTION:
XS GIS Cut Line= 3
      2816344.83     10175584.71      2815877.81     10175452.77
       2815501.1     10175270.49
#Sta/Elev= 30
    4359 1186.44  4389.3 1184.75  4441.2 1183.31  4456.8 1183.63  4503.6 1181.34
  4555.6 1180.67  4608.3 1178.43  4649.1 1177.38  4669.9 1177.91  4681.5 1176.78
  4732.2 1175.06  4827.8 1172.87  4876.2 1172.69  4898.8 1171.51  4913.3 1169.83
  4921.4 1170.09  4966.6 1166.11  4989.1 1163.16  5002.2 1163.28  5008.4 1162.44
  5008.9 1161.94  5025.6 1161.94  5026.1 1162.44  5039.9  1168.3  5046.6 1172.53
  5056.9 1174.35  5068.8 1178.88  5113.3 1181.85  5152.8 1183.16  5262.8  1184.5
#Mann= 3 ,-1 , 0
    4359     .05       0  5008.4     .05       0  5026.1     .05       0
Bank Sta=5008.4,5026.1
XS Rating Curve= 0 ,0
Exp/Cntr=0.3,0.1

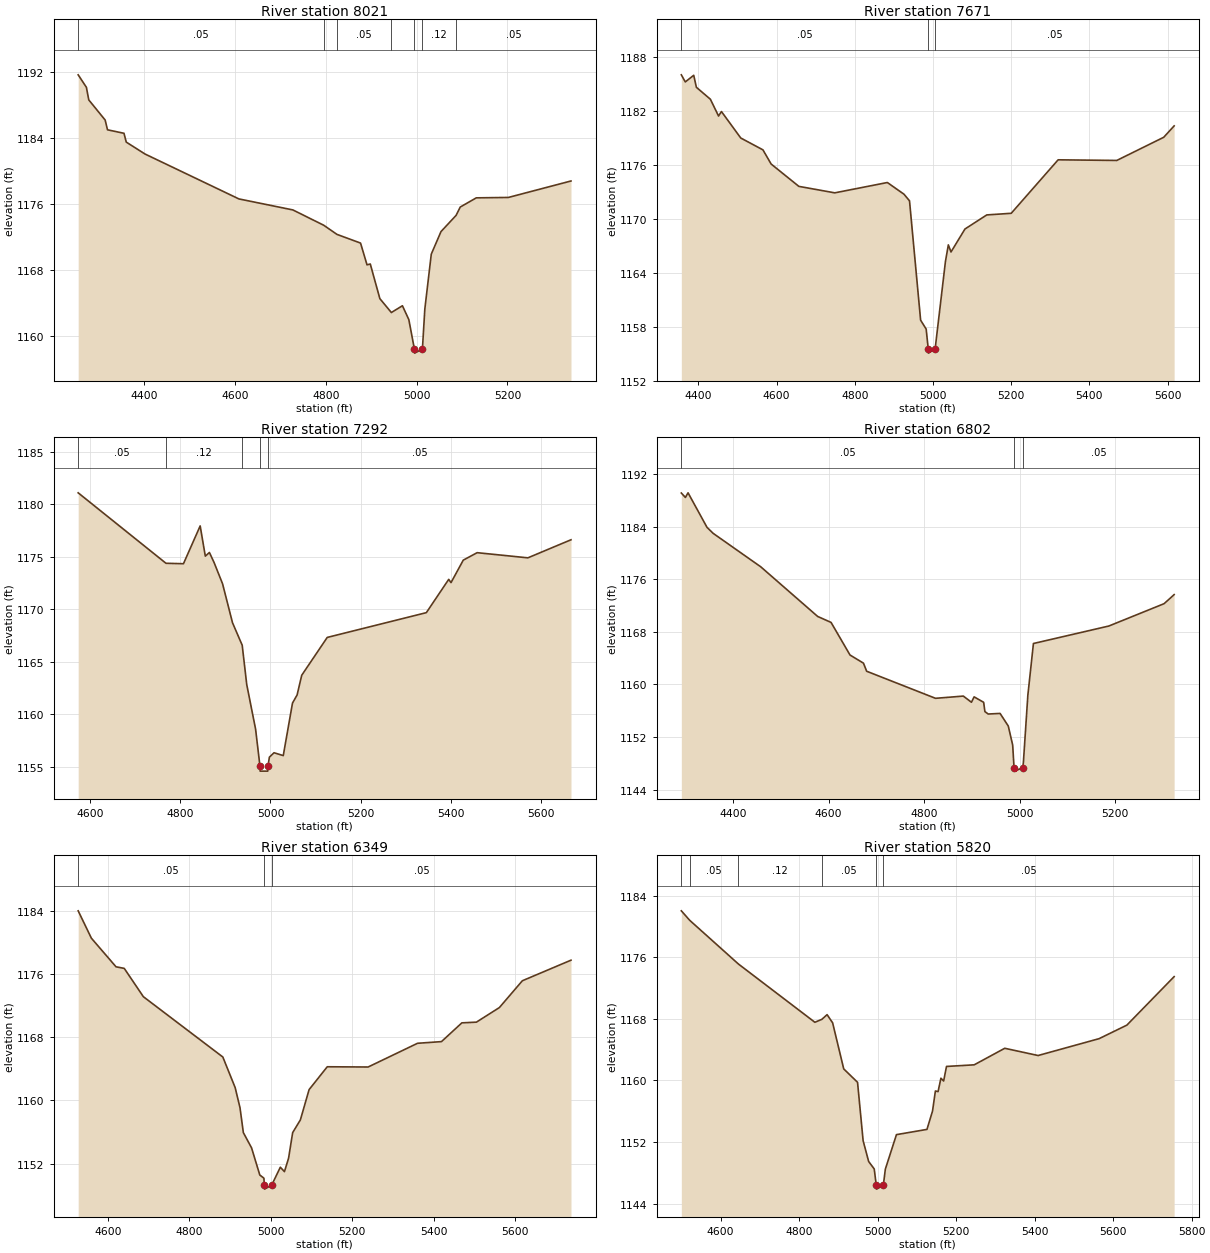
Type RM Length L Ch R = 1 ,8021    ,350,350,350
BEGIN DESCRIPTION:
HONDO CREEK 13.0
END DESCRIPTION:
XS GIS Cut Line= 3
       2816605.7     10175453.11      2816129.55     10175334.71
      2815699.86     10174924.08
#Sta/Elev= 30
  4254.9 1191.63    4273 1190.12  4278.2  1188.6  4314.3 1186.16  4319.5 1184.98
  4355.7 1184.56  4360.8 1183.49  4402.1 1182.05  4608.8 1176.62  4727.6 1175.29
  4795.4 1173.44  4824.7 1172.33  4876.6 1171.28  4890.8 1168.65    4898 1168.75
  4919.1 1164.56  4944.4 1162.88  4968.8  1163.7  4982.9 1162.02  4995.1 1158.47
  4995.6 1157.97  5012.8 1158.47  5018.1  1163.3  5032.3 1169.94  5053.7 1172.67
  5086.9 1174.63  5096.1 1175.64  5131.4 1176.75  5202.1  1176.8  5339.9 1178.79
#Mann= 7 ,-1 , 0
  4254.9     .05       0  4795.4     .12       0  4824.7     .05       0
  4944.4     .12       0  4995.1     .07       0  5012.8     .12       0
  5086.9     .05       0
Bank Sta=4995.1,5012.8
XS Rating Curve= 0 ,0
Exp/Cntr=0.3,0.1

Type RM Length L Ch R = 1 ,7671    ,379,379,379
BEGIN DESCRIPTION:
Mapping XS 89c73357
END DESCRIPTION:
XS GIS Cut Line= 3
      2816712.86     10175400.66      2816133.02     10174869.43
      2815659.01     10174869.43
#Sta/Elev= 30
  4356.3 1186.06  4366.4 1185.27    4388 1186.01  4394.8 1184.67  4430.6 1183.34
  4451.5 1181.47  4458.9 1181.97  4508.3 1179.02    4565  1177.7    4586 1176.12
  4656.9 1173.63  4748.8 1172.91  4883.2 1174.06  4925.7 1172.76  4939.9 1172.02
  4968.3 1158.72  4982.5 1157.73  4987.7 1155.55  4988.2 1155.05  5005.5 1155.55
  5031.8 1165.27  5039.2 1167.11    5046 1166.32  5081.7 1168.88  5137.5 1170.45
    5200 1170.63    5320 1176.59    5470 1176.52    5590  1179.1  5616.7 1180.37
#Mann= 3 ,-1 , 0
  4356.3     .05       0  4987.7     .05       0  5005.5     .05       0
Bank Sta=4987.7,5005.5
XS Rating Curve= 0 ,0
Exp/Cntr=0.3,0.1

Type RM Length L Ch R = 1 ,7292    ,490,490,490
BEGIN DESCRIPTION:
HONDO CREEK 12.0
END DESCRIPTION:
XS GIS Cut Line= 3
      2816850.08     10174567.34      2816322.26     10174685.41
      2815782.33     10174806.93
#Sta/Elev= 30
    4573 1181.08    4768 1174.37  4806.8 1174.33  4843.9 1177.93  4855.3 1175.05
  4864.4  1175.4  4874.7 1174.45  4893.6 1172.42  4915.7 1168.71  4937.2 1166.57
  4947.3 1162.82  4966.9 1158.59  4976.6 1155.08  4977.1 1154.58    4994 1154.58
  4994.5 1155.08  4997.6 1155.91  5007.9 1156.33  5028.4 1156.06  5048.9 1161.06
  5059.1 1161.83  5069.4 1163.71    5126 1167.31  5346.1 1169.67  5395.8 1172.84
  5400.9 1172.53  5428.1 1174.67  5458.9 1175.38  5571.6 1174.89  5667.3 1176.61
#Mann= 5 ,-1 , 0
    4573     .05       0    4768     .12       0  4937.2     .05       0
  4976.6     .03       0  4994.5     .05       0
Bank Sta=4976.6,4994.5
XS Rating Curve= 0 ,0
Exp/Cntr=0.3,0.1

Type RM Length L Ch R = 1 ,6802    ,453,453,453
BEGIN DESCRIPTION:
HONDO CREEK 11.0
END DESCRIPTION:
XS GIS Cut Line= 3
      2816705.68     10174053.11      2816134.76     10174327.77
       2815755.7     10174453.11
#Sta/Elev= 30
  4291.2 1189.12  4299.7 1188.45  4305.3 1189.15    4345  1183.9  4357.8 1182.99
  4457.7 1177.89  4576.9 1170.34    4605 1169.43  4644.7 1164.47  4672.9 1163.23
  4679.6    1162  4823.9 1157.88  4882.2 1158.22  4899.2 1157.28  4904.8  1158.1
  4924.8 1157.27  4927.4 1155.86  4934.3 1155.49  4959.2 1155.58  4976.4 1153.66
  4985.6 1150.77  4988.5  1147.3    4989  1146.8  5006.5  1147.3    5008 1148.06
  5017.4 1158.34  5029.1 1166.22  5187.1 1168.88  5302.9 1172.28    5324 1173.66
#Mann= 3 ,-1 , 0
  4291.2     .05       0  4988.5     .03       0  5006.5     .05       0
Bank Sta=4988.5,5006.5
XS Rating Curve= 0 ,0
Exp/Cntr=0.3,0.1

Type RM Length L Ch R = 1 ,6349    ,529,529,529
BEGIN DESCRIPTION:
HONDO CREEK 10.0
END DESCRIPTION:
XS GIS Cut Line= 3
      2816587.84     10173857.29      2815989.24     10173935.13
      2815499.11     10174291.95
#Sta/Elev= 30
  4526.9 1184.05  4559.3 1180.58  4619.8 1176.95    4640 1176.75  4686.9 1173.16
    4882 1165.51  4912.3 1161.63  4924.2 1159.07  4932.4 1155.92  4952.6 1153.98
  4972.8 1150.54  4982.9 1150.14  4983.9 1149.25  4984.4 1148.75  5001.9 1149.25
  5023.2 1151.53  5033.3 1150.97  5043.4 1152.66  5053.5 1155.92  5072.4 1157.53
  5093.8 1161.37  5138.4 1164.27  5238.8 1164.24  5360.1 1167.25  5418.8 1167.46
  5468.9 1169.84  5504.6 1169.93    5561 1171.78  5617.4 1175.18  5736.8 1177.79
#Mann= 3 ,-1 , 0
  4526.9     .05       0  4983.9     .05       0  5001.9     .05       0
Bank Sta=4983.9,5001.9
XS Rating Curve= 0 ,0
Exp/Cntr=0.3,0.1

Type RM Length L Ch R = 1 ,5820    ,475,475,475
BEGIN DESCRIPTION:
HONDO CREEK 9.0
END DESCRIPTION:
XS GIS Cut Line= 3
      2816405.63     10173383.33      2816070.52      10173324.3
      2815405.67     10173953.13
#Sta/Elev= 30
    4500 1182.04  4521.3 1180.81  4645.4 1175.13  4840.2 1167.56    4858 1167.94
  4871.3 1168.55  4885.4 1167.49  4913.7  1161.5  4948.9 1159.76  4963.1 1152.17
  4977.2 1149.47  4991.4  1148.5  4996.6 1146.38  4997.1 1145.88  5014.6 1146.38
  5019.7 1148.48    5048 1152.96  5125.7 1153.64  5139.9 1156.02  5147.2 1158.63
    5154 1158.55  5161.3 1160.29  5168.2 1159.93  5175.5 1161.82  5246.1 1162.03
  5323.9 1164.18  5408.9 1163.24  5564.2 1165.43    5635 1167.19  5755.4 1173.49
#Mann= 6 ,-1 , 0
    4500     .12       0  4521.3     .05       0  4645.4     .12       0
    4858     .05       0  4996.6     .03       0  5014.6     .05       0
Bank Sta=4996.6,5014.6
XS Rating Curve= 0 ,0
Exp/Cntr=0.3,0.1

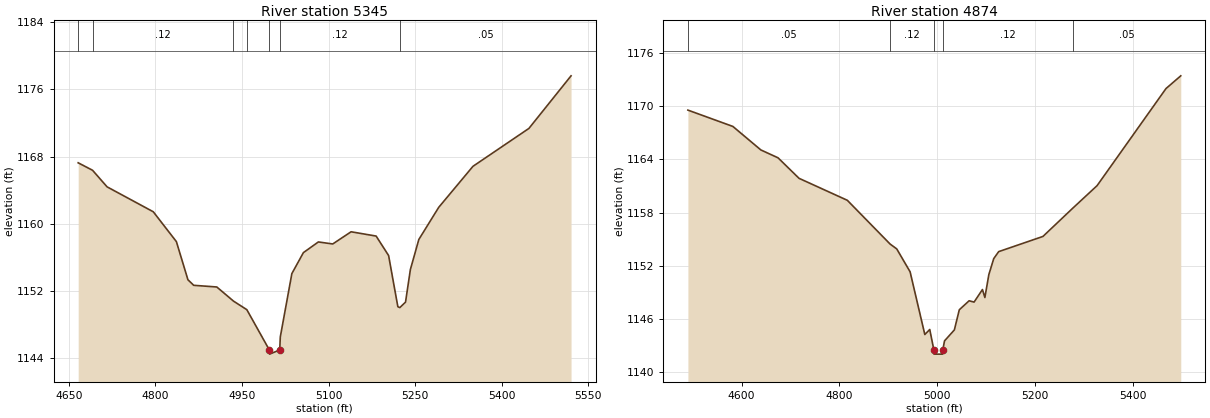
Type RM Length L Ch R = 1 ,5345    ,471,471,471
BEGIN DESCRIPTION:
HONDO CREEK 8.0
END DESCRIPTION:
XS GIS Cut Line= 3
      2816105.73     10173003.11      2815671.21     10173008.32
      2815305.72     10172803.13
#Sta/Elev= 30
  4666.2 1167.27  4691.1 1166.38  4716.2 1164.41  4796.3 1161.44  4836.3 1157.89
  4856.3 1153.35  4866.3 1152.69  4906.3 1152.49  4935.2 1150.81  4958.3 1149.79
  4997.3    1145  4997.8  1144.5  5015.3    1145  5016.3 1146.55  5036.3 1154.08
  5056.3 1156.58  5082.2 1157.85  5107.1 1157.61  5138.9 1159.06  5182.3 1158.55
  5203.9 1156.23  5219.9 1150.14  5223.3 1150.04  5233.2 1150.69  5241.6 1154.57
  5256.2 1158.14  5290.7 1161.97    5350 1166.85  5446.9 1171.36  5519.9 1177.62
#Mann= 7 ,-1 , 0
  4666.2     .05       0  4691.1     .12       0  4935.2     .05       0
  4958.3     .12       0  4997.3     .07       0  5015.3     .12       0
  5223.3     .05       0
Bank Sta=4997.3,5015.3
XS Rating Curve= 0 ,0
Exp/Cntr=0.3,0.1

Type RM Length L Ch R = 1 ,4874    ,494,494,494
BEGIN DESCRIPTION:
HONDO CREEK 7.0
END DESCRIPTION:
XS GIS Cut Line= 3
      2816273.64     10172765.27      2815996.83     10172531.17
      2815355.69     10172603.11
#Sta/Elev= 30
  4490.1 1169.59  4582.1 1167.74  4639.3 1165.08  4674.4 1164.19  4717.3 1161.87
  4816.1 1159.38  4903.5 1154.43  4917.1 1153.88  4944.4 1151.29  4974.5 1144.19
  4984.6 1144.76  4992.9 1142.47  4993.4 1141.97  5010.8 1141.97  5011.3 1142.47
  5014.8 1143.47  5034.9 1144.71    5045 1146.99  5065.1 1148.01  5075.2 1147.86
  5092.3 1149.28  5097.3 1148.38  5105.4 1150.97  5115.4 1152.78  5125.5 1153.57
    5216 1155.29  5277.6 1158.52  5326.7 1161.04  5467.6 1172.03  5497.8 1173.47
#Mann= 5 ,-1 , 0
  4490.1     .05       0  4903.5     .12       0  4992.9     .07       0
  5011.3     .12       0  5277.6     .05       0
Bank Sta=4992.9,5011.3
XS Rating Curve= 0 ,0
Exp/Cntr=0.3,0.1