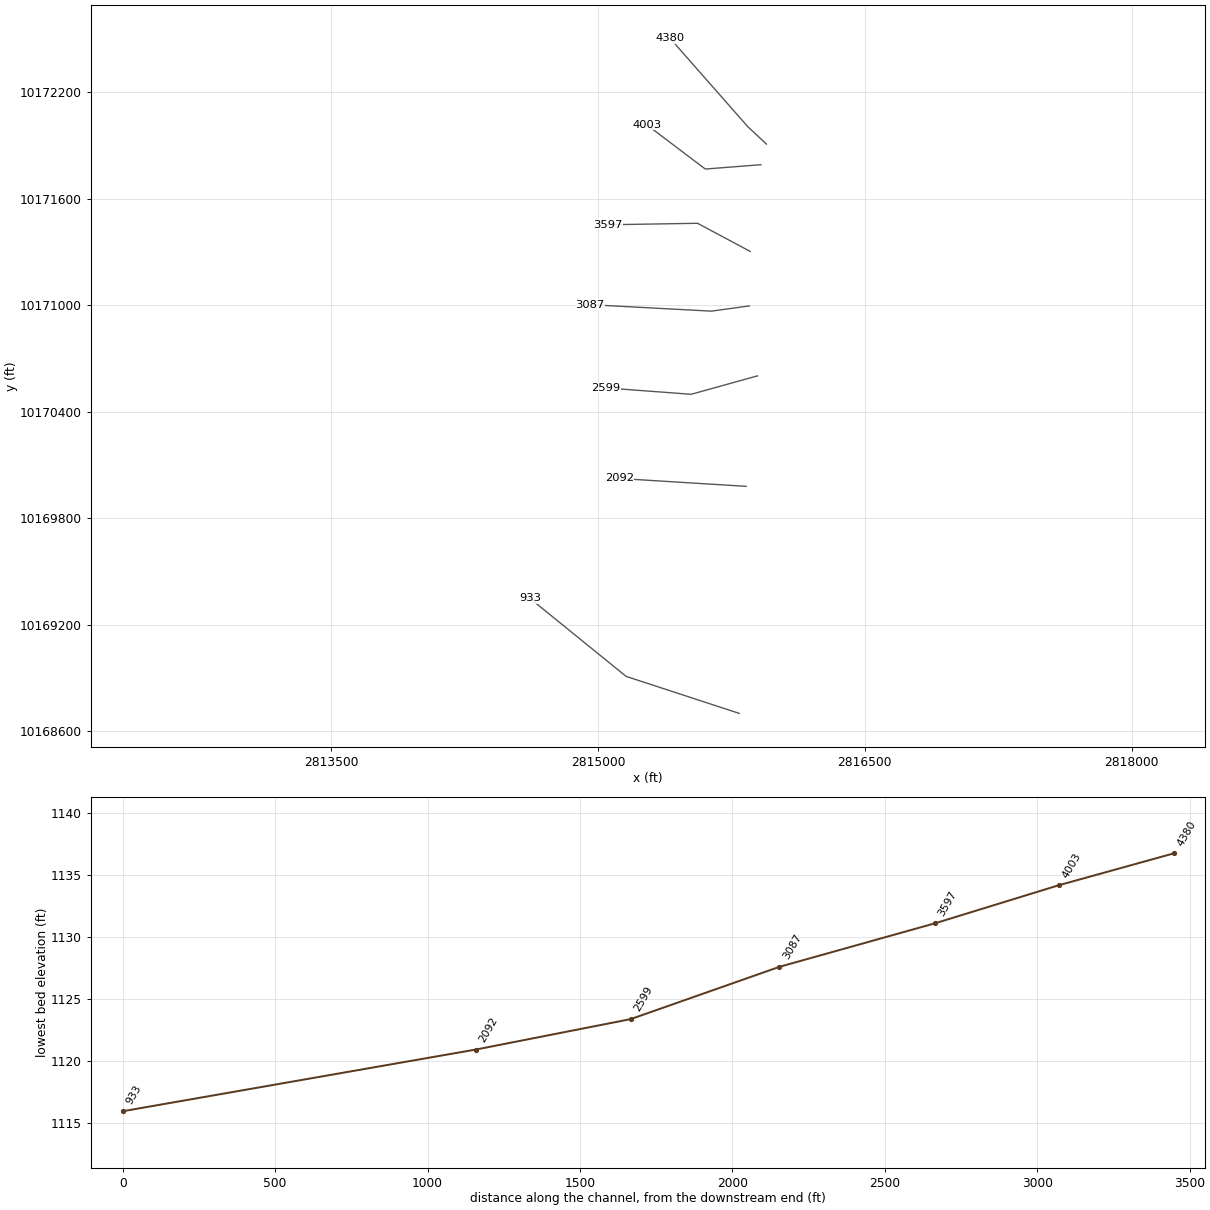
HEC-RAS study HONDO CREEK.prj: HONDO CREEK Base Level Engineering

--- HONDO CREEK.g01 (geometry) --- (continued)

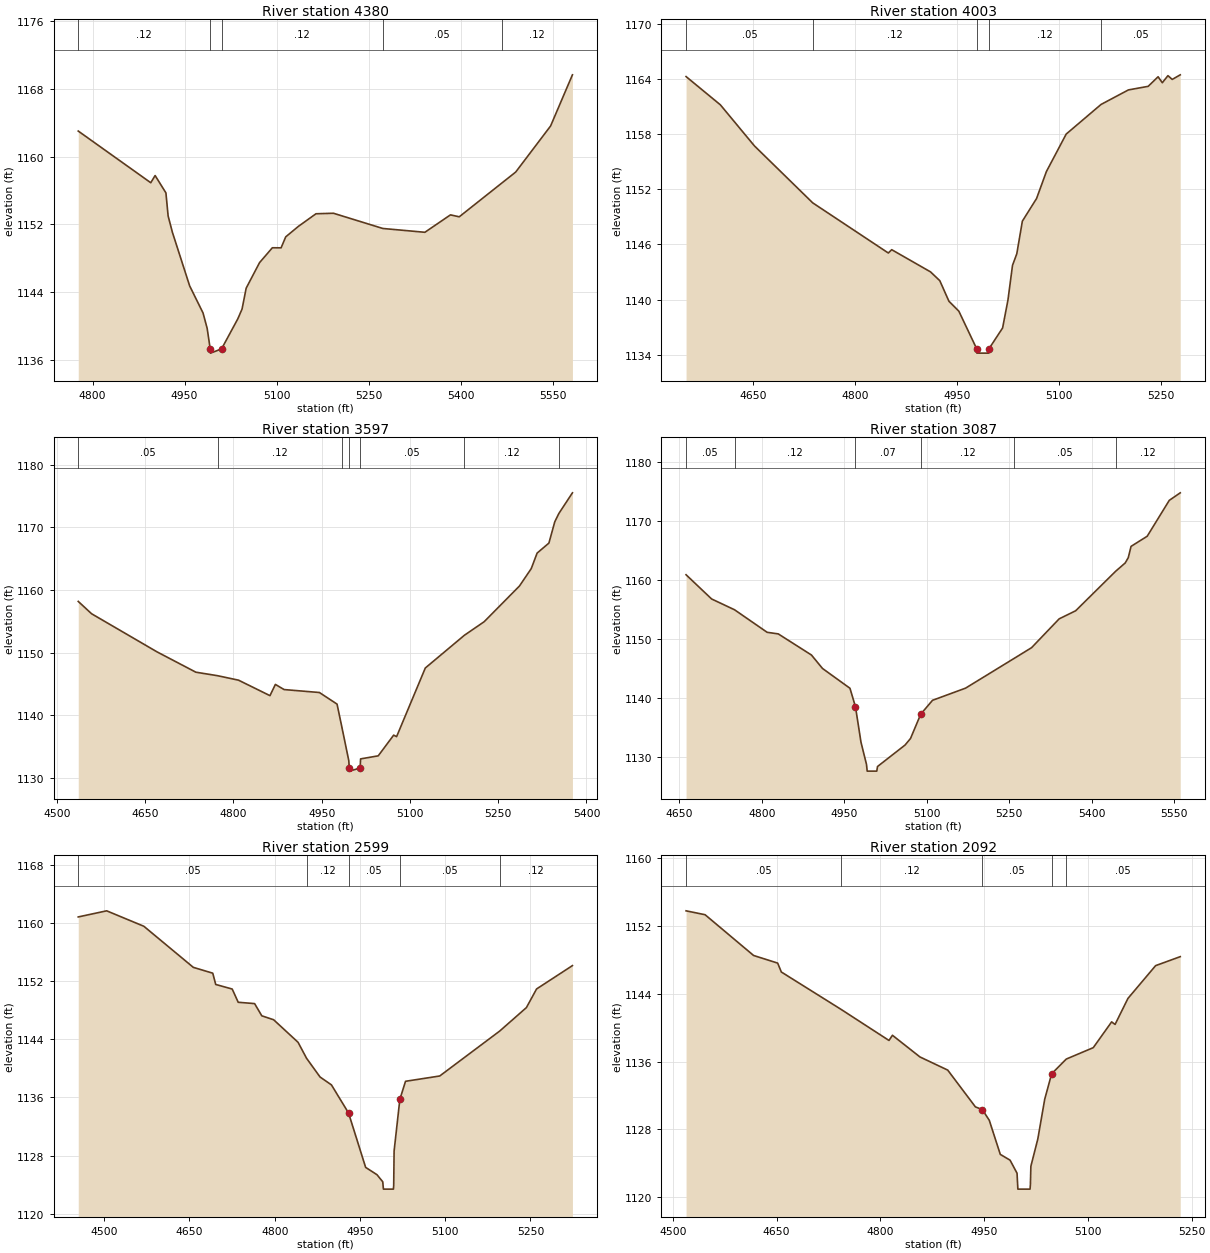
Type RM Length L Ch R = 1 ,4380    ,377,377,377
BEGIN DESCRIPTION:
HONDO CREEK 6.0
END DESCRIPTION:
XS GIS Cut Line= 3
      2815947.27     10171907.62      2815842.82     10172005.15
      2815405.69      10172503.1
#Sta/Elev= 30
  4776.7 1163.02  4894.9 1156.91    4902 1157.76  4919.6 1155.71  4923.2 1152.98
  4930.2 1151.04  4958.3 1144.71  4980.1 1141.51  4986.8  1139.7  4991.8 1137.26
  4992.3 1136.76  5010.3 1137.26  5036.6 1140.79  5043.7 1141.97  5050.4 1144.44
  5072.2 1147.46  5093.1 1149.22  5107.3 1149.21  5114.9 1150.51  5135.7 1151.76
  5164.2 1153.24  5192.7  1153.3  5273.2  1151.5  5341.7 1151.05  5383.4 1153.11
  5397.7 1152.88  5466.7 1156.85  5489.7 1158.17  5546.6 1163.62  5582.2 1169.67
#Mann= 5 ,-1 , 0
  4776.7     .12       0  4991.8     .07       0  5010.3     .12       0
  5273.2     .05       0  5466.7     .12       0
Bank Sta=4991.8,5010.3
XS Rating Curve= 0 ,0
Exp/Cntr=0.3,0.1

Type RM Length L Ch R = 1 ,4003    ,406,406,406
BEGIN DESCRIPTION:
HONDO CREEK 5.0
END DESCRIPTION:
XS GIS Cut Line= 3
      2815916.03     10171791.31      2815603.51       10171767.
      2815273.61     10172017.03
#Sta/Elev= 30
  4551.4 1164.24  4601.9 1161.17    4652 1156.71  4737.8 1150.52  4849.1 1145.07
  4854.1 1145.43  4911.2 1143.02  4924.9 1142.06  4938.3 1139.83  4952.9 1138.75
    4979 1134.69  4979.5 1134.19    4997 1134.19  4997.5 1134.69  5017.3 1136.92
  5025.2 1139.96  5031.9 1143.73  5038.2 1144.98  5046.4 1148.53  5067.3 1150.99
  5081.8 1153.92  5110.9 1157.99  5162.2 1161.21  5202.5 1162.79  5231.6 1163.18
  5246.2 1164.22  5252.4 1163.57  5260.7 1164.34    5267 1163.93  5278.8 1164.43
#Mann= 5 ,-1 , 0
  4551.4     .05       0  4737.8     .12       0    4979     .07       0
  4997.5     .12       0  5162.2     .05       0
Bank Sta=4979,4997.5
XS Rating Curve= 0 ,0
Exp/Cntr=0.3,0.1

Type RM Length L Ch R = 1 ,3597    ,510,510,510
BEGIN DESCRIPTION:
HONDO CREEK 4.0
END DESCRIPTION:
XS GIS Cut Line= 3
      2815855.69     10171303.11       2815560.1     10171461.45
       2815055.7     10171453.11
#Sta/Elev= 30
  4536.3 1158.19    4559 1156.22  4670.4 1150.13  4736.2  1146.9    4773 1146.34
  4808.6 1145.63  4862.1 1143.16  4871.3 1144.95  4886.1 1144.13  4946.1 1143.66
  4976.1 1141.81  4984.1 1138.23  4996.1 1132.77  4996.8 1131.62  4997.3 1131.12
  5015.3 1131.62  5016.1 1133.07  5046.1 1133.56  5072.3 1136.86  5077.3 1136.62
  5126.1 1147.57  5192.5 1152.79  5226.1 1154.95  5286.1 1160.65  5306.1 1163.42
  5316.1  1165.9  5336.1 1167.49  5346.1 1170.89    5353 1172.21  5376.1 1175.51
#Mann= 7 ,-1 , 0
  4536.3     .05       0    4773     .12       0  4984.1     .05       0
  4996.8     .05       0  5015.3     .05       0  5192.5     .12       0
    5353     .05       0
Bank Sta=4996.8,5015.3
XS Rating Curve= 0 ,0
Exp/Cntr=0.3,0.1

Type RM Length L Ch R = 1 ,3087    ,488,488,488
BEGIN DESCRIPTION:
HONDO CREEK 3.0
END DESCRIPTION:
XS GIS Cut Line= 3
      2815851.76     10170996.17      2815638.23     10170966.66
      2814955.66     10171003.11
#Sta/Elev= 30
  4662.2 1160.91  4708.7  1156.8  4750.4 1154.97  4809.7 1151.15  4829.9 1150.88
  4890.3  1147.3  4910.4 1145.02  4960.4 1141.66  4970.4 1138.53  4980.5 1132.49
  4990.5 1128.74  4991.7 1127.61  5009.2 1127.61  5010.5 1128.39  5060.6 1132.03
  5070.6 1133.15  5089.1 1137.26  5110.6 1139.62  5170.7 1141.68    5259 1146.72
  5290.9 1148.55    5341 1153.43    5371  1154.8    5444 1161.52  5461.1  1162.9
  5466.8 1163.82  5471.8 1165.72  5501.2 1167.44  5541.3 1173.52  5561.3  1174.8
#Mann= 6 ,-1 , 0
  4662.2     .05       0  4750.4     .12       0  4970.4     .07       0
  5089.1     .12       0    5259     .05       0    5444     .12       0
Bank Sta=4970.4,5089.1
XS Rating Curve= 0 ,0
Exp/Cntr=0.3,0.1

Type RM Length L Ch R = 1 ,2599    ,507,507,507
BEGIN DESCRIPTION:
HONDO CREEK 2.0
END DESCRIPTION:
XS GIS Cut Line= 3
      2815896.89     10170602.07      2815524.24     10170498.38
      2815042.79     10170534.36
#Sta/Elev= 30
  4454.3  1160.8  4504.3 1161.64  4569.7 1159.52  4656.8 1153.87    4691 1153.07
  4696.2 1151.52  4725.2 1150.89  4735.8 1149.07  4764.6 1148.89  4777.3 1147.21
  4798.1 1146.67  4841.1 1143.57    4856 1141.38  4879.8  1138.8  4899.8 1137.72
  4929.9 1133.86    4960 1126.38    4980 1125.37  4990.1  1124.4  4991.3 1123.39
  5008.9 1123.39  5009.4 1123.89  5010.1 1128.63  5020.2 1135.72  5030.2 1138.21
  5090.4 1138.94    5196 1145.12  5242.9 1148.34  5260.8  1150.9  5323.9 1154.11
#Mann= 5 ,-1 , 0
  4454.3     .05       0    4856     .12       0  4929.9     .05       0
  5020.2     .05       0    5196     .12       0
Bank Sta=4929.9,5020.2
XS Rating Curve= 0 ,0
Exp/Cntr=0.3,0.1

Type RM Length L Ch R = 1 ,2092    ,1159,1159,1159
BEGIN DESCRIPTION:
Mapping XS dfe7f53e
END DESCRIPTION:
XS GIS Cut Line= 2
      2815833.12     10169979.93      2815120.19     10170024.17
#Sta/Elev= 30
  4519.2 1153.79  4546.7 1153.33  4616.8 1148.52  4651.6 1147.62  4656.9 1146.57
    4743 1142.17  4812.5 1138.49  4817.5  1139.1  4857.3 1136.54  4897.4 1134.99
  4937.4 1130.65  4947.5 1130.32  4957.5 1129.06  4973.4 1125.04  4987.5 1124.36
  4997.6 1122.82  4998.8 1120.94  5016.4 1120.94  5016.9 1121.44  5017.6 1123.64
  5027.6 1126.85  5037.6 1131.55  5047.6 1134.55  5068.7 1136.29  5107.8 1137.64
  5134.3 1140.68  5139.3 1140.38  5157.9 1143.45  5197.9 1147.32  5233.5 1148.38
#Mann= 5 ,-1 , 0
  4519.2     .05       0    4743     .12       0  4947.5     .05       0
  5047.6     .12       0  5068.7     .05       0
Bank Sta=4947.5,5047.6
XS Rating Curve= 0 ,0
Exp/Cntr=0.3,0.1

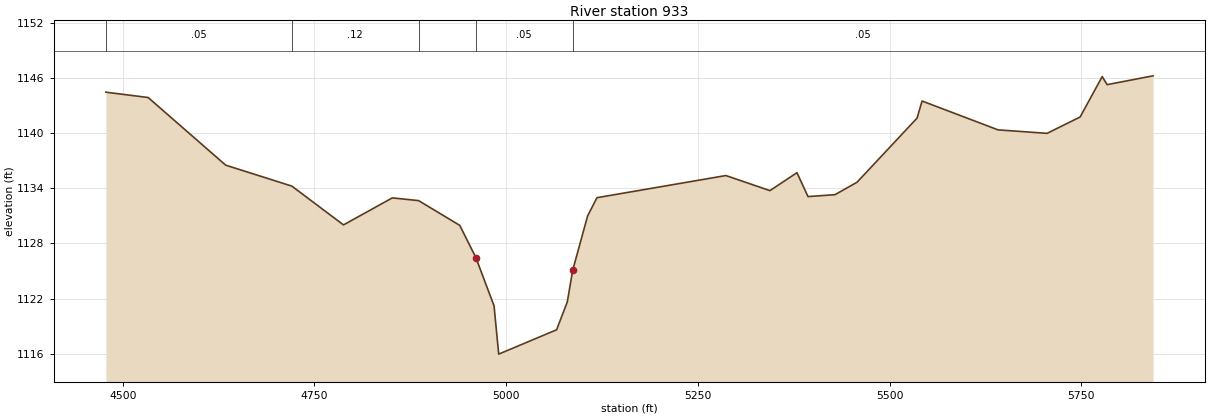
Type RM Length L Ch R = 1 ,933     ,0,0,0
BEGIN DESCRIPTION:
HONDO CREEK 1.0
END DESCRIPTION:
XS GIS Cut Line= 3
       2815794.1     10168701.28      2815158.67     10168909.62
      2814617.96     10169348.94
#Sta/Elev= 30
  4478.1 1144.46  4533.2 1143.88  4634.3 1136.52  4720.6 1134.24  4787.9 1130.02
  4851.6 1132.96  4885.9 1132.66  4939.5 1129.97  4960.5 1126.46  4984.2 1121.22
  4990.3 1115.96  5065.8 1118.61  5079.7 1121.63  5086.8 1125.09  5106.2 1130.99
  5118.4 1132.98  5286.5 1135.39  5343.9 1133.75  5379.2  1135.7  5393.6  1133.1
  5428.8 1133.31  5457.5 1134.66  5535.8 1141.64  5542.3  1143.5  5641.4 1140.36
  5705.3 1139.98  5748.4 1141.76  5777.2 1146.16  5783.6 1145.28  5843.5 1146.24
#Mann= 5 ,-1 , 0
  4478.1     .05       0  4720.6     .12       0  4885.9     .05       0
  4960.5     .05       0  5086.8     .05       0
Bank Sta=4960.5,5086.8
XS Rating Curve= 0 ,0
Exp/Cntr=0.3,0.1

Chan Stop Cuts=-1
Use User Specified Reach Order=0
Composite Channel Slope=5