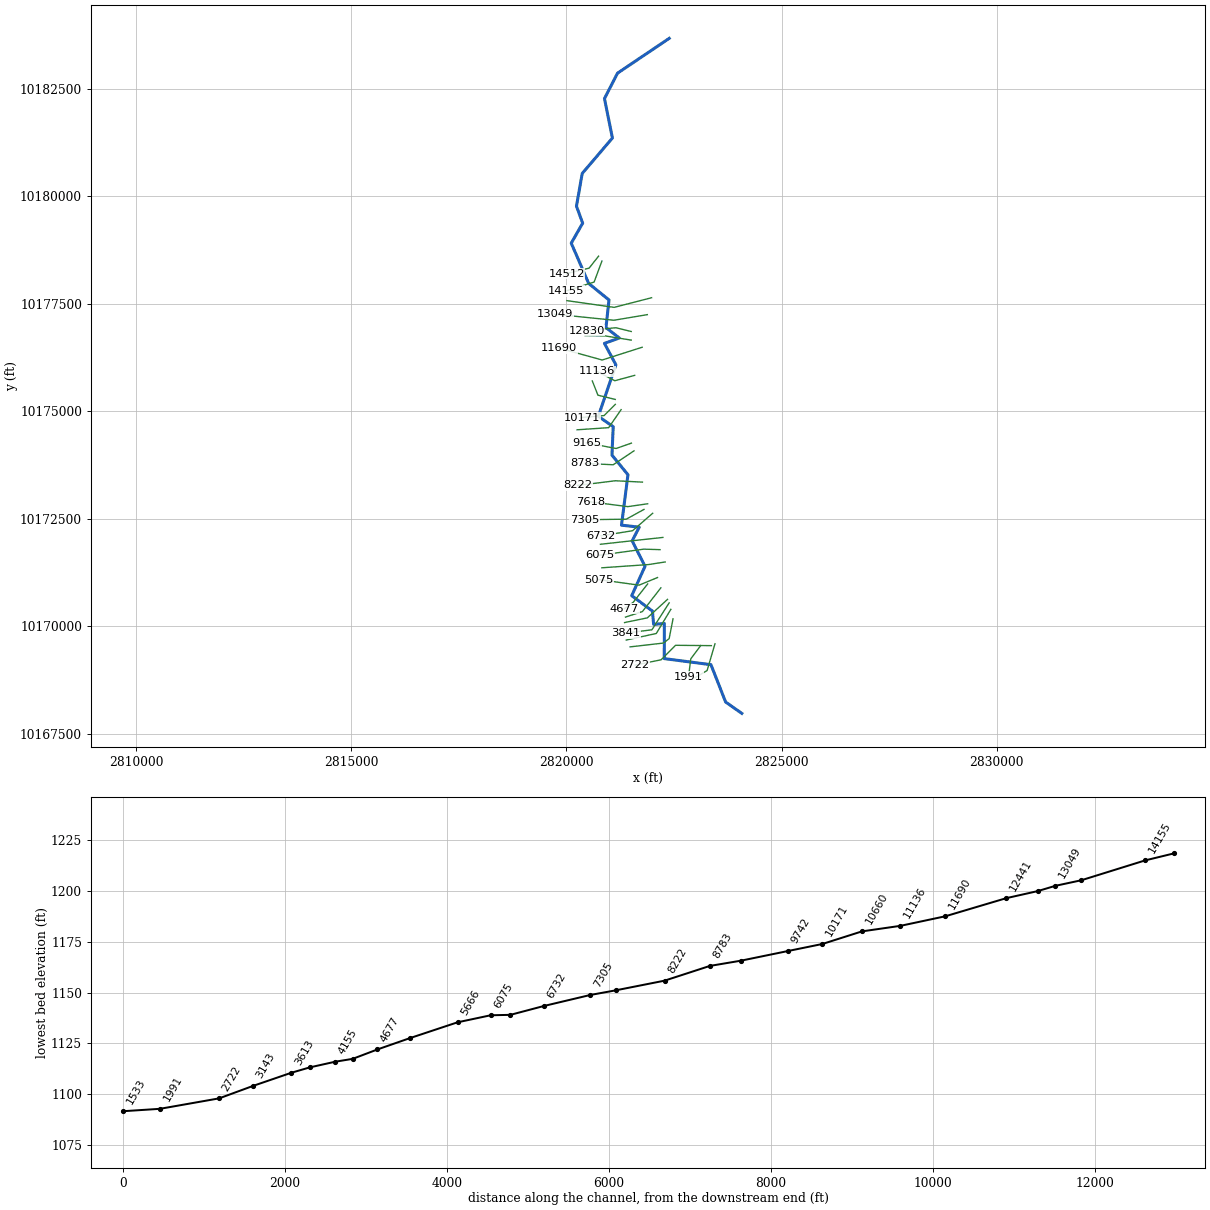
--- JOHNSON CREEK.prj (project) ---

Proj Title=JOHNSON CREEK Base Level Engineering
Current Plan=p01
Default Exp/Contr=0.3,0.1
English Units
Geom File=g01
Flow File=f01
Plan File=p01
Y Axis Title=Elevation
X Axis Title(PF)=Main Channel Distance
X Axis Title(XS)=Station
BEGIN DESCRIPTION:
JOHNSON CREEK
END DESCRIPTION:
DSS Export Rating Curves= 0
DSS Export Rating Curve Sorted= 0
DSS Export Volume Flow Curves= 0
DXF OffsetX= 0
DXF OffsetY= 0
DXF ScaleX= 1
DXF ScaleY= 10

--- JOHNSON CREEK.p01 (plan) ---

Plan Title=Multiple Run
Short Identifier=Multiple
Geom File=g01
Flow File=f01
Subcritical Flow
K Sum by GR= 0
Std Step Tol= 0.01
Critical Tol= 0.01
Num of Std Step Trials= 20
Max Error Tol= 0.3
Flow Tol Ratio= 0.001
Split Flow NTrial= 30
Split Flow Tol= 0.02
Split Flow Ratio= 0.02
Log Output Level= 0
Friction Slope Method= 1
Unsteady Friction Slope Method= 2
Unsteady Bridges Friction Slope Method= 1
Parabolic Critical Depth
Global Vel Dist=  1 , 1 , 1
Global Log Level= 0
CheckData=True
Encroach Param= -1, 0, 0, 0
BEGIN DESCRIPTION:
Multiple Run
END DESCRIPTION:

--- JOHNSON CREEK.f01 (steady flow) ---

Flow Title=Multiple
Program Version=4.10
Number of Profiles= 7
Profile Names=10-year,25-year,50-year,1pct_min,100-year,1pct_plu,500-year
River Rch & RM=JOHNSON CREEK,Reach-1         ,14512
     518     851    2047    1636    2952    5327    4387
River Rch & RM=JOHNSON CREEK,Reach-1         ,10171
     760    1288    2744    2004    3965    7847    5838
River Rch & RM=JOHNSON CREEK,Reach-1         ,2722
    1633    2899    6446    4584    9533   19826   13873
River Rch & RM=JOHNSON CREEK,Reach-1         ,1991
    1633    2899    6446    4584    9533   19826   13873
Boundary for River Rch & Prof#=JOHNSON CREEK,Reach-1         , 1
Up Type= 0
Dn Type= 3
Dn Slope=0.005
Boundary for River Rch & Prof#=JOHNSON CREEK,Reach-1         , 2
Up Type= 0
Dn Type= 3
Dn Slope=0.005
Boundary for River Rch & Prof#=JOHNSON CREEK,Reach-1         , 3
Up Type= 0
Dn Type= 3
Dn Slope=0.005
Boundary for River Rch & Prof#=JOHNSON CREEK,Reach-1         , 4
Up Type= 0
Dn Type= 3
Dn Slope=0.005
Boundary for River Rch & Prof#=JOHNSON CREEK,Reach-1         , 5
Up Type= 0
Dn Type= 3
Dn Slope=0.005
Boundary for River Rch & Prof#=JOHNSON CREEK,Reach-1         , 6
Up Type= 0
Dn Type= 3
Dn Slope=0.005
Boundary for River Rch & Prof#=JOHNSON CREEK,Reach-1         , 7
Up Type= 0
Dn Type= 3
Dn Slope=0.005
DSS Import GetInterval= 0
DSS Import GetPeak= 0
DSS Import FillOption= 0

--- JOHNSON CREEK.g01 (geometry) ---

Geom Title=Existing Conditions
Program Version=4.10

River Reach=JOHNSON CREEK   ,Reach-1
Reach XY= 30
      2822389.25       10183669.      2821186.75       10182859.
      2820883.25       10182268.        2821068.       10181351.
        2820366.       10180528.        2820232.       10179766.
       2820376.5       10179372.        2820111.       10178907.
      2820516.75       10177970.      2820988.75       10177586.
      2820917.75       10176944.        2821228.       10176702.
      2820882.75       10176577.        2821149.       10176079.
        2820740.       10174882.      2821086.25       10174640.
       2821057.5       10173979.      2821429.25       10173523.
      2821279.25       10172351.      2821691.75       10172304.
      2821526.75       10171986.      2821826.25       10171395.
      2821516.75       10170711.        2821998.       10170354.
      2822026.25       10170045.      2822276.25       10170064.
      2822273.25       10169248.      2823359.25       10169107.
      2823699.75       10168239.        2824076.       10167975.

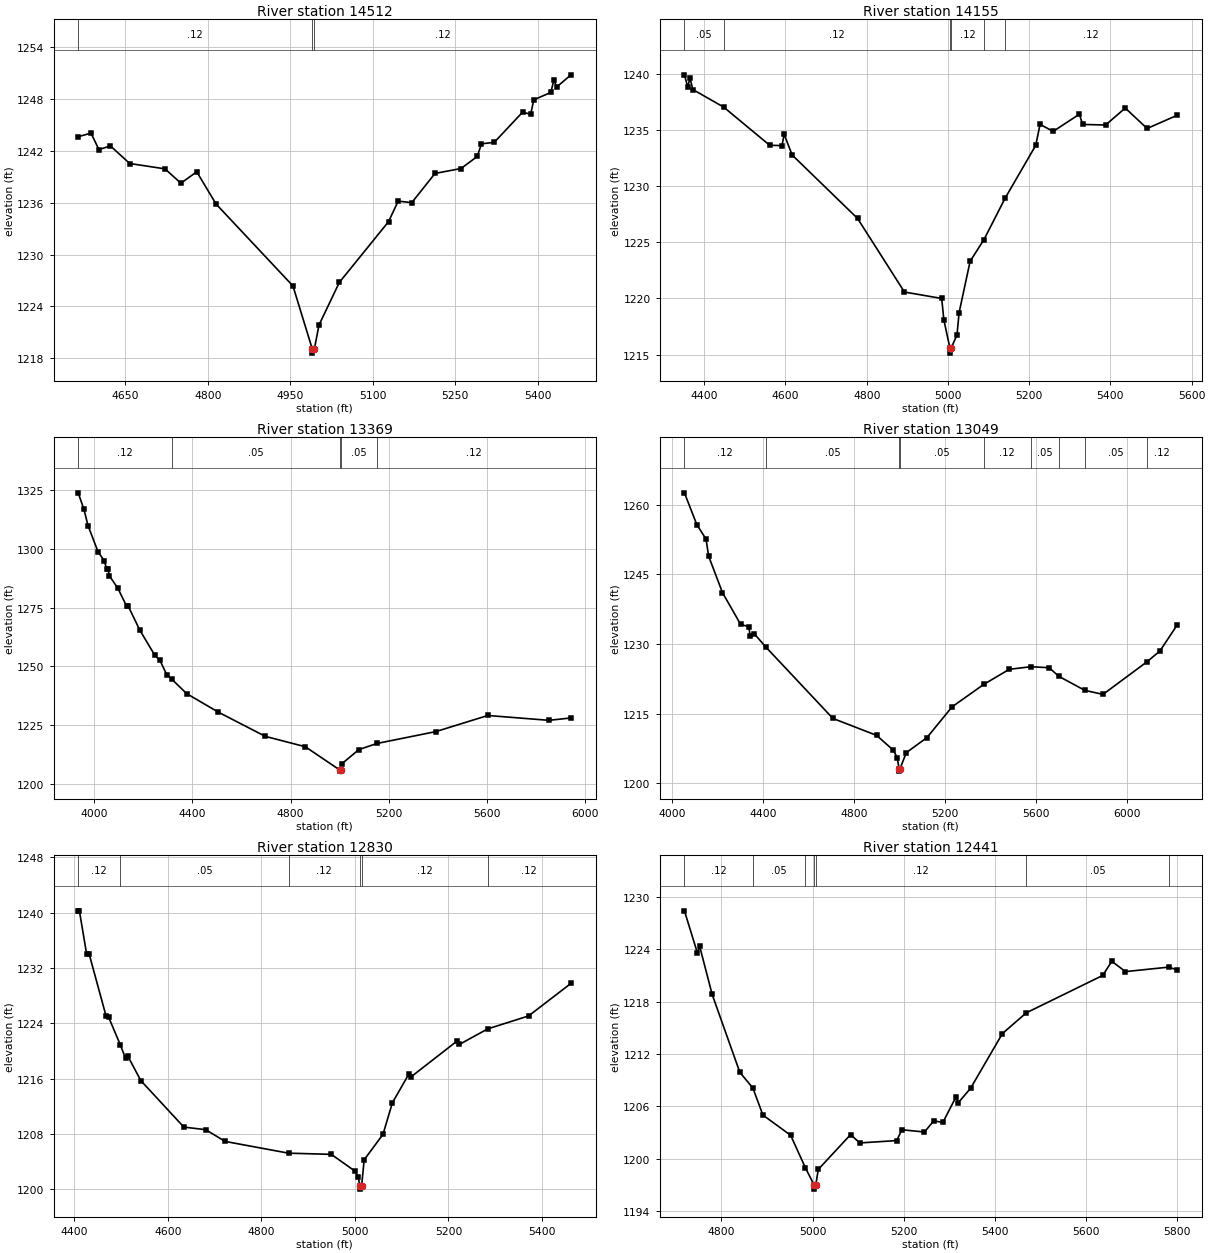
Type RM Length L Ch R = 1 ,14512   ,357,357,357
BEGIN DESCRIPTION:
JOHNSON CREEK 29.0
END DESCRIPTION:
XS GIS Cut Line= 3
      2820746.62     10178604.48      2820525.27     10178325.84
      2819999.96     10178201.01
#Sta/Elev= 30
  4564.4 1243.66  4587.7 1244.08  4602.1 1242.17  4622.9  1242.6  4658.1 1240.56
  4722.2 1239.94  4751.1 1238.28  4779.9  1239.6  4815.1 1235.86  4954.8 1226.38
  4989.8  1219.1    4990  1218.6  4993.8  1219.1  5002.1 1221.85  5039.1 1226.79
  5128.6 1233.83    5146  1236.2  5170.8 1236.03    5213 1239.41  5260.3 1239.98
  5289.9 1241.38  5297.4 1242.84  5320.7 1243.01  5372.1  1246.5  5386.9 1246.27
  5392.6 1247.94  5423.5 1248.79  5429.1 1250.22  5434.2 1249.42  5460.2 1250.83
#Mann= 3 ,-1 , 0
  4564.4     .12       0  4989.8     .07       0  4993.8     .12       0
Bank Sta=4989.8,4993.8
XS Rating Curve= 0 ,0
Exp/Cntr=0.3,0.1

Type RM Length L Ch R = 1 ,14155   ,786,786,786
BEGIN DESCRIPTION:
JOHNSON CREEK 28.0
END DESCRIPTION:
XS GIS Cut Line= 3
      2820824.74     10178492.48      2820642.46     10178002.92
      2819983.61     10177794.59
#Sta/Elev= 30
  4351.2 1239.92  4359.4 1238.83  4364.7 1239.65  4371.9 1238.61  4447.6 1237.05
    4561 1233.65  4591.4 1233.61  4596.7 1234.63  4616.4 1232.78  4777.4 1227.13
    4893 1220.57  4984.7    1220  4989.9  1218.1  5004.6 1215.63  5004.8 1215.13
  5008.6 1215.63  5022.3 1216.76  5027.5 1218.74  5054.6 1223.31  5088.8 1225.25
  5140.8 1228.93  5216.2 1233.64  5226.8 1235.51    5259 1234.88  5323.6 1236.41
  5331.7  1235.5  5388.2 1235.45  5436.6 1236.96  5490.4 1235.14  5564.6 1236.32
#Mann= 6 ,-1 , 0
  4351.2     .05       0  4447.6     .12       0  5004.6     .07       0
  5008.6     .12       0  5088.8     .05       0  5140.8     .12       0
Bank Sta=5004.6,5008.6
XS Rating Curve= 0 ,0
Exp/Cntr=0.3,0.1

Type RM Length L Ch R = 1 ,13369   ,320,320,320
BEGIN DESCRIPTION:
JOHNSON CREEK 27.0
END DESCRIPTION:
XS GIS Cut Line= 3
      2821978.42     10177638.35      2821108.61     10177414.38
      2820010.14     10177570.56
#Sta/Elev= 30
    3935 1323.86  3958.5 1316.81    3975 1309.92  4015.7 1298.82  4041.1 1294.95
  4051.3 1291.32  4056.4  1291.5  4061.7 1288.61  4097.1 1283.14  4132.7 1275.52
  4137.8 1275.84  4185.7 1265.46  4247.6 1254.62  4268.3 1252.48  4295.5  1246.5
  4316.9 1244.45  4376.9 1238.37  4505.8 1230.49  4697.4 1220.17  4860.5 1215.75
  5000.3 1205.87  5000.5 1205.37  5004.3 1205.87  5007.9  1208.4  5078.6 1214.55
  5152.9 1217.16  5391.7 1222.19  5603.8 1229.06  5852.7    1227  5942.7 1228.01
#Mann= 5 ,-1 , 0
    3935     .12       0  4316.9     .05       0  5000.3     .05       0
  5004.3     .05       0  5152.9     .12       0
Bank Sta=5000.3,5004.3
XS Rating Curve= 0 ,0
Exp/Cntr=0.3,0.1

Type RM Length L Ch R = 1 ,13049   ,219,219,219
BEGIN DESCRIPTION:
JOHNSON CREEK 26.0
END DESCRIPTION:
XS GIS Cut Line= 3
       2821879.4      10177245.1       2821103.4      10177114.9
      2819731.03     10177255.53
#Sta/Elev= 30
  4055.8 1262.58  4110.3 1255.73  4150.8 1252.61  4162.3 1248.92  4222.9  1241.1
  4302.9 1234.23  4339.1 1233.74  4344.2 1231.83  4363.8 1232.17  4413.4 1229.37
  4708.5 1213.98  4900.7 1210.33  4974.1 1207.14  4991.1 1205.56  4999.2 1203.13
  4999.4 1202.63  5003.2 1203.13  5031.3 1206.62  5121.8 1209.85  5232.4 1216.48
  5371.3  1221.3  5483.7 1224.56  5578.3 1225.12  5659.3 1224.91  5701.2 1223.06
  5815.8 1220.03  5895.8 1219.16  6088.3 1226.15  6145.8 1228.49  6222.2 1234.14
#Mann= 9 ,-1 , 0
  4055.8     .12       0  4413.4     .05       0  4999.2     .05       0
  5003.2     .05       0  5371.3     .12       0  5578.3     .05       0
  5701.2     .12       0  5815.8     .05       0  6088.3     .12       0
Bank Sta=4999.2,5003.2
XS Rating Curve= 0 ,0
Exp/Cntr=0.3,0.1

Type RM Length L Ch R = 1 ,12830   ,389,389,389
BEGIN DESCRIPTION:
JOHNSON CREEK 25.0
END DESCRIPTION:
XS GIS Cut Line= 3
      2821505.71     10176853.11      2821150.27     10176940.42
      2820465.36     10176875.32
#Sta/Elev= 30
    4408 1240.27  4410.6 1240.27  4426.2 1233.96  4431.4 1234.04  4467.8 1225.01
  4472.9 1224.93    4498  1220.9  4509.3 1218.94  4514.5 1219.22  4541.9 1215.72
    4634 1208.99  4680.7 1208.62  4722.2 1206.92  4857.9 1205.22  4949.4 1205.05
  4999.6 1202.64  5007.2 1201.72  5010.2 1200.52  5010.5 1200.02  5014.2 1200.52
  5019.7 1204.27  5059.9 1207.94    5080 1212.51  5115.3 1216.67  5120.3 1216.28
  5218.4 1221.44  5223.4 1220.95  5283.7 1223.19  5371.3 1225.07    5462 1229.78
#Mann= 6 ,-1 , 0
    4408     .12       0    4498     .05       0  4857.9     .12       0
  5010.2     .07       0  5014.2     .12       0  5283.7     .12       0
Bank Sta=5010.2,5014.2
XS Rating Curve= 0 ,0
Exp/Cntr=0.3,0.1

Type RM Length L Ch R = 1 ,12441   ,751,751,751
BEGIN DESCRIPTION:
JOHNSON CREEK 24.0
END DESCRIPTION:
XS GIS Cut Line= 3
      2821505.71     10176653.11      2820900.27     10176750.32
      2820432.13     10176758.12
#Sta/Elev= 30
  4718.8  1228.4  4747.3 1223.57  4752.3 1224.32  4779.6 1218.83  4840.4  1209.9
    4869 1208.11    4891 1205.01  4951.8  1202.7  4984.1 1198.99  5003.1 1197.03
  5003.3 1196.53  5007.1 1197.03  5012.5 1198.79  5083.4 1202.77  5103.7 1201.82
  5184.7 1202.09  5195.9 1203.33  5245.5 1203.07  5265.7 1204.34    5286 1204.18
  5314.7 1207.09  5319.8 1206.43  5346.6 1208.07  5416.6 1214.35    5469 1216.72
  5636.6    1221  5656.6 1222.62  5686.6 1221.44  5781.1 1221.95  5800.2 1221.64
#Mann= 7 ,-1 , 0
  4718.8     .12       0    4869     .05       0  4984.1     .12       0
  5003.1     .07       0  5007.1     .12       0    5469     .05       0
  5781.1     .12       0
Bank Sta=5003.1,5007.1
XS Rating Curve= 0 ,0
Exp/Cntr=0.3,0.1

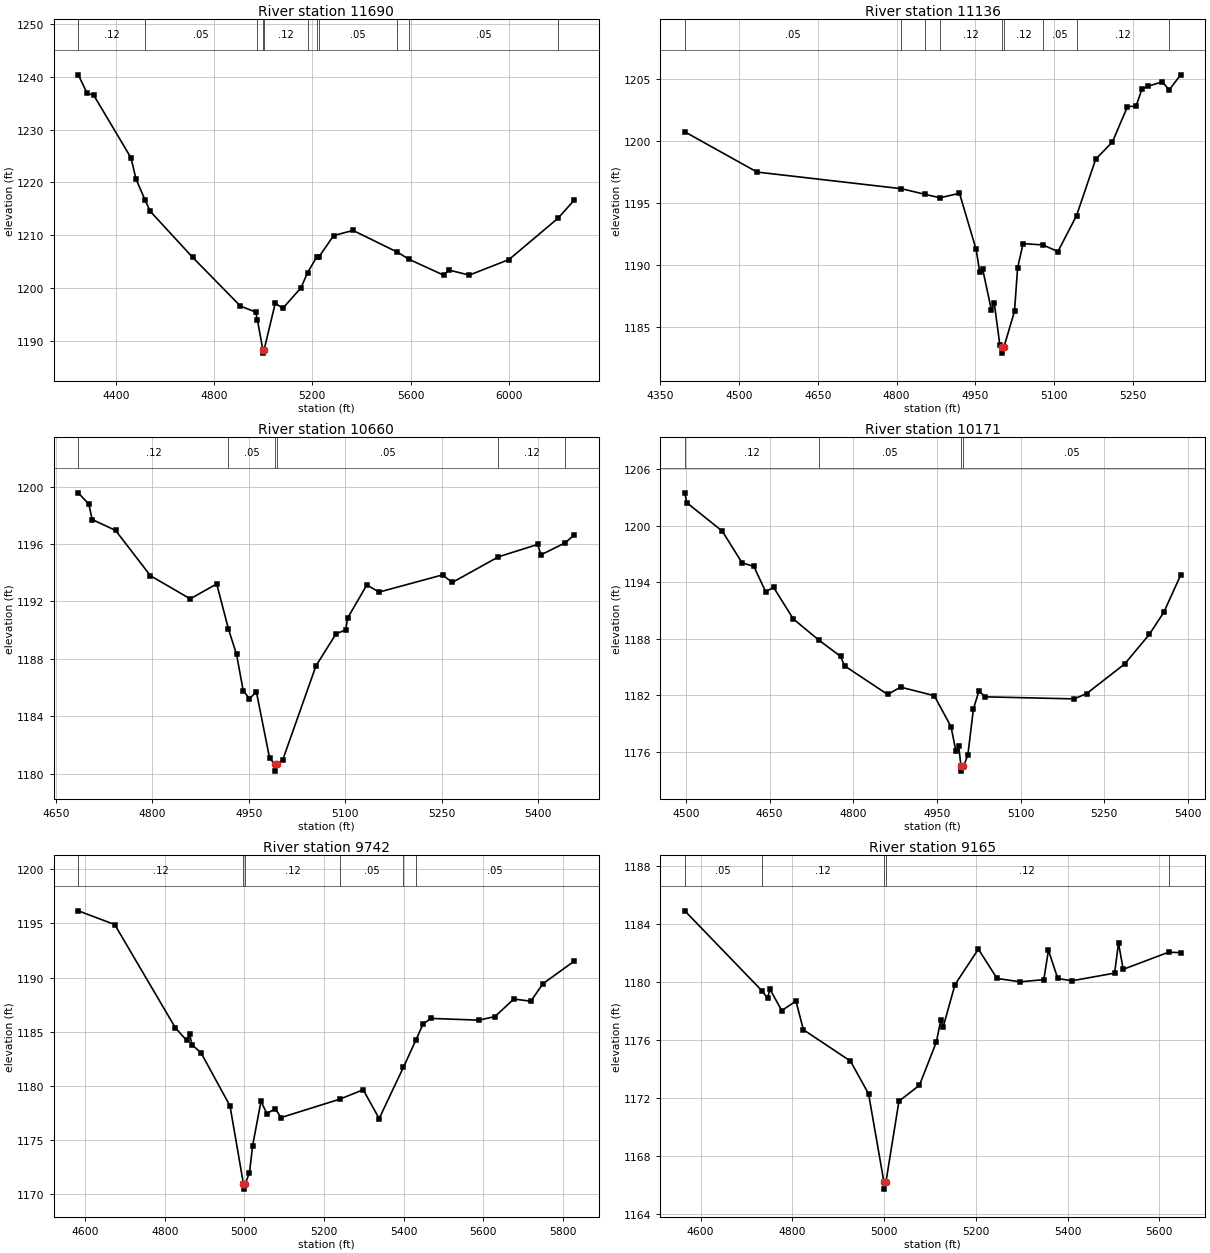
Type RM Length L Ch R = 1 ,11690   ,554,554,554
BEGIN DESCRIPTION:
JOHNSON CREEK 23.0
END DESCRIPTION:
XS GIS Cut Line= 3
      2821759.69     10176487.31      2820829.96     10176190.42
      2819823.89     10176468.59
#Sta/Elev= 30
  4246.7 1240.38  4282.4 1236.89  4309.2 1236.53  4460.9 1224.67  4481.9 1220.59
  4519.1 1216.58  4539.8 1214.49  4712.8 1205.76    4907 1196.54  4968.6 1195.42
  4976.1 1193.97  4998.8 1188.12  4999.1 1187.62  5002.8 1188.12  5048.7 1197.05
  5080.2 1196.14  5153.7 1200.01  5180.5 1202.88  5217.8 1205.84  5226.9 1205.87
  5286.6  1209.9  5365.6 1210.88  5546.1 1206.77  5594.6 1205.39  5734.8  1202.4
  5756.3 1203.37  5839.3 1202.41  6001.1 1205.36  6201.1 1213.21  6266.5 1216.61
#Mann= 11 ,-1 , 0
  4246.7     .12       0  4519.1     .05       0  4976.1     .12       0
  4998.8     .07       0  5002.8     .12       0  5180.5     .05       0
  5217.8     .12       0  5226.9     .05       0  5546.1     .12       0
  5594.6     .05       0  6201.1     .12       0
Bank Sta=4998.8,5002.8
XS Rating Curve= 0 ,0
Exp/Cntr=0.3,0.1

Type RM Length L Ch R = 1 ,11136   ,476,476,476
BEGIN DESCRIPTION:
JOHNSON CREEK 22.0
END DESCRIPTION:
XS GIS Cut Line= 3
       2821585.2     10175833.66      2821124.23     10175708.65
      2820710.44     10175924.66
#Sta/Elev= 30
  4396.6 1200.73  4534.2 1197.49  4809.3 1196.15  4854.8 1195.69  4882.7 1195.42
  4919.8 1195.78  4951.5 1191.26  4958.3 1189.46    4964 1189.66  4980.4 1186.42
  4986.1 1186.92  4996.7 1183.56  5000.5 1183.41  5000.8 1182.91  5004.5 1183.41
  5024.6 1186.28  5030.5 1189.78    5041 1191.73    5079 1191.62  5107.3 1191.09
  5142.8 1193.99  5179.2 1198.52    5211 1199.91  5239.8 1202.76  5256.1  1202.8
  5267.5 1204.19  5278.3 1204.39  5306.1 1204.76  5319.2  1204.1    5341 1205.32
#Mann= 9 ,-1 , 0
  4396.6     .05       0  4809.3     .12       0  4854.8     .05       0
  4882.7     .12       0  5000.5     .07       0  5004.5     .12       0
    5079     .05       0  5142.8     .12       0  5319.2     .05       0
Bank Sta=5000.5,5004.5
XS Rating Curve= 0 ,0
Exp/Cntr=0.3,0.1

Type RM Length L Ch R = 1 ,10660   ,489,489,489
BEGIN DESCRIPTION:
JOHNSON CREEK 21.0
END DESCRIPTION:
XS GIS Cut Line= 3
      2821134.67     10175273.75        2820731.     10175372.72
      2820600.78     10175703.48
#Sta/Elev= 30
  4684.7 1199.57  4701.1 1198.77  4706.2 1197.71  4742.6 1196.95  4796.9 1193.79
  4858.7 1192.18  4899.9 1193.22  4918.2 1190.07  4930.8  1188.3  4941.1 1185.78
  4950.6 1185.23  4961.7 1185.68  4982.2 1181.06  4990.2 1180.67  4990.4 1180.17
  4994.2 1180.67  5002.8 1180.98  5054.3 1187.51  5085.7 1189.76  5100.3    1190
  5103.7 1190.86  5133.4 1193.15  5152.4 1192.65  5251.2 1193.85  5266.2 1193.32
  5338.1 1195.11  5398.9 1195.97  5404.3 1195.25    5442 1196.09  5455.8 1196.63
#Mann= 6 ,-1 , 0
  4684.7     .12       0  4918.2     .05       0  4990.2     .05       0
  4994.2     .05       0  5338.1     .12       0    5442     .05       0
Bank Sta=4990.2,4994.2
XS Rating Curve= 0 ,0
Exp/Cntr=0.3,0.1

Type RM Length L Ch R = 1 ,10171   ,429,429,429
BEGIN DESCRIPTION:
JOHNSON CREEK 20.0
END DESCRIPTION:
XS GIS Cut Line= 3
      2821134.67     10175159.19      2820874.23     10174898.76
      2820355.65     10174853.11
#Sta/Elev= 30
  4497.9 1203.51  4501.5 1202.46  4565.1 1199.44  4600.5 1196.08  4621.7  1195.7
  4642.9    1193    4657 1193.48  4692.4 1190.12  4737.6  1187.9  4777.3 1186.14
  4784.3 1185.14  4861.6  1182.1  4884.8 1182.88  4945.1 1181.97  4975.2 1178.68
  4983.9 1176.08  4988.9 1176.63  4993.1 1174.46  4993.4 1173.96  4997.5 1174.46
  5005.3 1175.66  5015.3 1180.55  5025.4 1182.52  5035.4 1181.85    5196 1181.63
  5218.4  1182.2  5286.4 1185.33  5330.6 1188.47  5356.6 1190.82  5386.8 1194.77
#Mann= 4 ,-1 , 0
  4497.9     .12       0  4737.6     .05       0  4993.1     .05       0
  4997.5     .05       0
Bank Sta=4993.1,4997.5
XS Rating Curve= 0 ,0
Exp/Cntr=0.3,0.1

Type RM Length L Ch R = 1 ,9742    ,577,577,577
BEGIN DESCRIPTION:
JOHNSON CREEK 19.0
END DESCRIPTION:
XS GIS Cut Line= 3
      2821270.09     10175036.82        2820981.     10174617.51
      2820247.28     10174568.07
#Sta/Elev= 30
  4583.2 1196.17  4674.5  1194.9  4826.7 1185.37  4854.9  1184.2  4862.5 1184.77
  4868.6  1183.8  4891.4 1183.04    4964 1178.14  4997.6 1170.96  4997.9 1170.46
    5002 1170.96  5012.8 1171.97  5020.7 1174.47  5041.7 1178.57  5056.6 1177.44
  5077.5 1177.89  5092.1 1177.07  5239.5 1178.77  5298.3 1179.64  5338.4 1176.98
  5399.4 1181.73  5430.9 1184.25  5448.6 1185.72  5468.7 1186.23    5589 1186.07
    5629  1186.4  5676.4 1188.02  5719.2 1187.82  5749.3 1189.43  5827.9 1191.52
#Mann= 6 ,-1 , 0
  4583.2     .12       0  4997.6     .07       0    5002     .12       0
  5239.5     .05       0  5399.4     .12       0  5430.9     .05       0
Bank Sta=4997.6,5002
XS Rating Curve= 0 ,0
Exp/Cntr=0.3,0.1

Type RM Length L Ch R = 1 ,9165    ,382,382,382
BEGIN DESCRIPTION:
JOHNSON CREEK 18.0
END DESCRIPTION:
XS GIS Cut Line= 3
      2821509.63     10174258.13      2821152.88     10174133.13
      2820462.75     10174265.95
#Sta/Elev= 30
  4565.4  1184.9    4733 1179.41  4745.7 1178.89    4751  1179.5  4776.7 1178.03
  4807.7 1178.68  4823.9 1176.71  4926.5 1174.55    4966 1172.29  4999.4 1166.23
  4999.7 1165.73  5003.9 1166.23  5032.2 1171.79  5076.8 1172.88  5113.7 1175.86
  5123.6 1177.39  5128.7 1176.91  5154.4 1179.82  5205.3 1182.26  5246.1 1180.24
    5297 1180.01  5347.9 1180.16  5358.1 1182.18  5378.4 1180.24    5409 1180.08
  5502.3 1180.61  5510.8 1182.68    5521 1180.87    5620 1182.05  5646.2 1182.02
#Mann= 5 ,-1 , 0
  4565.4     .05       0    4733     .12       0  4999.4     .07       0
  5003.9     .12       0    5620     .05       0
Bank Sta=4999.4,5003.9
XS Rating Curve= 0 ,0
Exp/Cntr=0.3,0.1

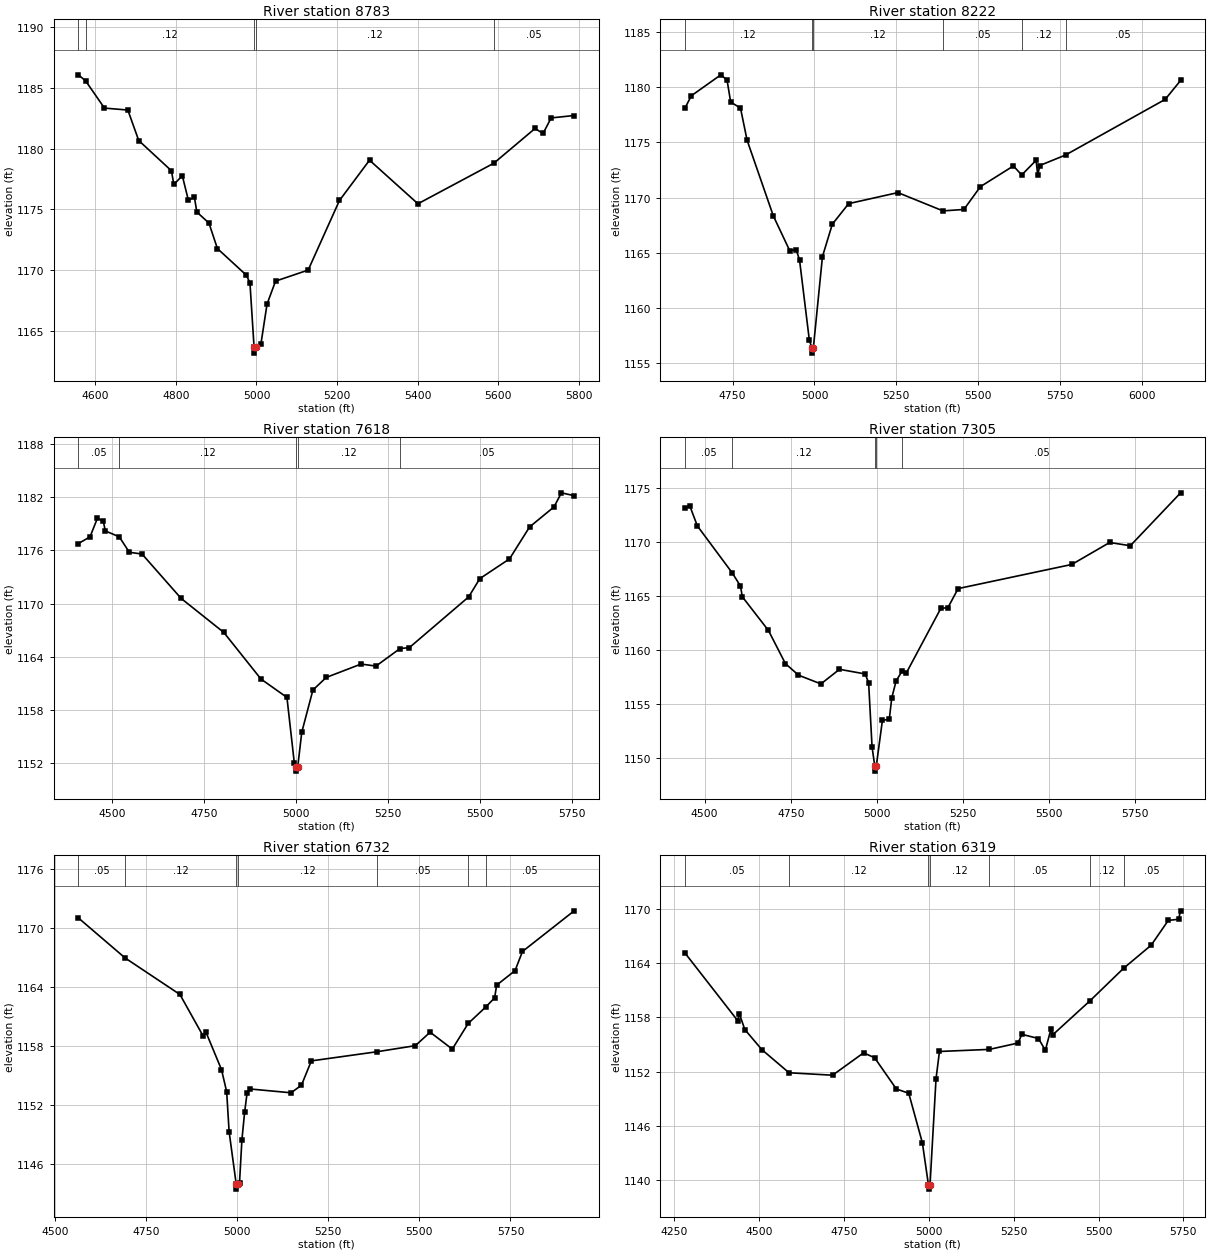
Type RM Length L Ch R = 1 ,8783    ,561,561,561
BEGIN DESCRIPTION:
JOHNSON CREEK 17.0
END DESCRIPTION:
XS GIS Cut Line= 3
      2821569.59     10174078.47      2821085.54     10173754.87
      2820438.67     10173786.68
#Sta/Elev= 30
  4558.2 1186.08  4576.1 1185.59    4623 1183.34    4681 1183.18    4708 1180.67
  4789.1 1178.18  4795.1 1177.05  4816.1 1177.77  4831.1 1175.76  4846.2 1175.98
  4852.2 1174.78  4882.2 1173.87  4903.2 1171.77  4975.3 1169.57  4983.9 1168.94
  4994.1 1163.66  4994.4 1163.16  4998.6 1163.66  5011.3 1163.95  5026.3  1167.2
  5047.4 1169.09  5128.3    1170  5205.9 1175.73  5280.5 1179.05  5400.6 1175.46
  5588.8  1178.8    5691 1181.66    5711 1181.25    5731 1182.53  5788.1 1182.73
#Mann= 5 ,-1 , 0
  4558.2     .05       0  4576.1     .12       0  4994.1     .07       0
  4998.6     .12       0  5588.8     .05       0
Bank Sta=4994.1,4998.6
XS Rating Curve= 0 ,0
Exp/Cntr=0.3,0.1

Type RM Length L Ch R = 1 ,8222    ,604,604,604
BEGIN DESCRIPTION:
JOHNSON CREEK 16.0
END DESCRIPTION:
XS GIS Cut Line= 3
       2821765.6     10173351.45      2821134.65     10173383.13
      2820258.87     10173273.99
#Sta/Elev= 30
  4603.9 1178.09  4623.8 1179.24    4714 1181.14  4732.9 1180.67    4744 1178.67
    4774 1178.12  4794.1 1175.21  4874.2 1168.34  4924.2 1165.19  4944.2 1165.26
  4954.3 1164.34  4984.3 1157.05    4992 1156.38  4992.4 1155.88  4996.6 1156.38
  5024.3 1164.64  5054.4 1167.58  5104.4 1169.45  5254.8 1170.45  5392.5 1168.79
  5456.3 1168.92  5506.7 1170.99  5607.5 1172.87  5632.8 1172.05  5676.8 1173.38
  5681.8 1172.03  5688.1 1172.91  5766.6 1173.86    6071 1178.91  6118.2 1180.63
#Mann= 6 ,-1 , 0
  4603.9     .12       0    4992     .07       0  4996.6     .12       0
  5392.5     .05       0  5632.8     .12       0  5766.6     .05       0
Bank Sta=4992,4996.6
XS Rating Curve= 0 ,0
Exp/Cntr=0.3,0.1

Type RM Length L Ch R = 1 ,7618    ,313,313,313
BEGIN DESCRIPTION:
JOHNSON CREEK 15.0
END DESCRIPTION:
XS GIS Cut Line= 3
      2821887.12     10172847.97      2821426.32     10172781.57
      2820551.32     10172893.55
#Sta/Elev= 30
    4409 1176.76  4440.8 1177.52    4461 1179.63  4477.1 1179.25  4482.2 1178.19
  4520.3 1177.52  4547.6 1175.78  4582.2 1175.58  4688.4 1170.58  4804.5 1166.74
  4905.4 1161.49    4976 1159.42  4996.2 1151.98  5000.7 1151.61    5001 1151.11
  5005.4 1151.61  5016.3 1155.49  5046.6 1160.25  5082.8 1161.67  5177.6 1163.18
    5218 1162.95  5283.5 1164.93  5308.7 1165.03    5470 1170.75  5500.3 1172.81
  5580.9 1175.03  5635.7 1178.64  5701.9 1180.89  5722.1 1182.48  5756.7 1182.16
#Mann= 5 ,-1 , 0
    4409     .05       0  4520.3     .12       0  5000.7     .07       0
  5005.4     .12       0  5283.5     .05       0
Bank Sta=5000.7,5005.4
XS Rating Curve= 0 ,0
Exp/Cntr=0.3,0.1

Type RM Length L Ch R = 1 ,7305    ,573,573,573
BEGIN DESCRIPTION:
JOHNSON CREEK 14.0
END DESCRIPTION:
XS GIS Cut Line= 3
      2821801.34     10172716.48      2821389.86      10172489.9
      2820419.58      10172476.9
#Sta/Elev= 30
  4442.3 1173.16  4457.1 1173.32  4478.8 1171.49  4579.6 1167.17  4603.8 1165.95
  4609.5 1164.94  4685.2 1161.83  4734.5 1158.77  4772.4  1157.7  4837.7 1156.89
  4891.6 1158.24  4966.2 1157.81  4976.2    1157  4986.2 1151.06  4993.9 1149.33
  4994.2 1148.83  4998.6 1149.33  5016.2 1153.51  5036.2 1153.64  5043.5 1155.61
  5056.2 1157.18  5073.8 1158.09  5086.2 1157.93  5186.2 1163.89  5206.2 1163.92
  5236.2  1165.7  5566.3 1167.93  5676.3 1169.96  5736.3 1169.66  5882.4 1174.55
#Mann= 5 ,-1 , 0
  4442.3     .05       0  4579.6     .12       0  4993.9     .07       0
  4998.6     .12       0  5073.8     .05       0
Bank Sta=4993.9,4998.6
XS Rating Curve= 0 ,0
Exp/Cntr=0.3,0.1

Type RM Length L Ch R = 1 ,6732    ,413,413,413
BEGIN DESCRIPTION:
JOHNSON CREEK 13.0
END DESCRIPTION:
XS GIS Cut Line= 3
      2822004.47     10172627.95      2821536.92     10172221.84
      2820805.69     10172103.11
#Sta/Elev= 30
  4564.6 1171.02  4692.9 1166.94  4843.3 1163.22  4907.4 1158.96  4914.5  1159.4
  4957.3 1155.57  4971.5 1153.32  4978.2 1149.25  4997.7  1143.9    4998  1143.4
  5002.4  1143.9  5006.7 1144.04  5013.3 1148.42  5020.9 1151.28  5027.5 1153.19
  5035.2  1153.6  5148.1 1153.21  5176.6 1153.98  5203.8 1156.46  5383.7 1157.39
  5489.1 1158.01  5529.6 1159.38  5590.4 1157.66    5634 1160.27  5681.7 1161.93
  5706.6 1162.88    5712 1164.17  5762.6 1165.65  5782.9  1167.6  5924.7 1171.74
#Mann= 7 ,-1 , 0
  4564.6     .05       0  4692.9     .12       0  4997.7     .07       0
  5002.4     .12       0  5383.7     .05       0    5634     .12       0
  5681.7     .05       0
Bank Sta=4997.7,5002.4
XS Rating Curve= 0 ,0
Exp/Cntr=0.3,0.1

Type RM Length L Ch R = 1 ,6319    ,244,244,244
BEGIN DESCRIPTION:
JOHNSON CREEK 12.0
END DESCRIPTION:
XS GIS Cut Line= 3
      2822241.46     10172065.43      2821595.59     10171995.11
      2820789.51      10171906.7
#Sta/Elev= 30
  4281.2 1165.12    4437 1157.63  4442.1 1158.37    4458 1156.65  4508.3 1154.43
  4588.3 1151.88  4716.5 1151.61  4807.9 1154.08  4840.3 1153.54  4904.4 1150.09
  4940.9 1149.62  4981.1 1144.14  4998.8 1139.54  4999.2 1139.04  5003.6 1139.54
  5021.3 1151.23  5031.4 1154.23  5178.7 1154.46  5262.8 1155.16  5274.1 1156.12
  5323.1 1155.66  5343.3 1154.36  5360.2 1156.76  5365.2 1156.07  5475.3 1159.84
  5574.1 1163.42  5655.1 1165.96  5705.4 1168.69  5735.6 1168.82  5741.8 1169.75
#Mann= 7 ,-1 , 0
  4281.2     .05       0  4588.3     .12       0  4998.8     .07       0
  5003.6     .12       0  5178.7     .05       0  5475.3     .12       0
  5574.1     .05       0
Bank Sta=4998.8,5003.6
XS Rating Curve= 0 ,0
Exp/Cntr=0.3,0.1

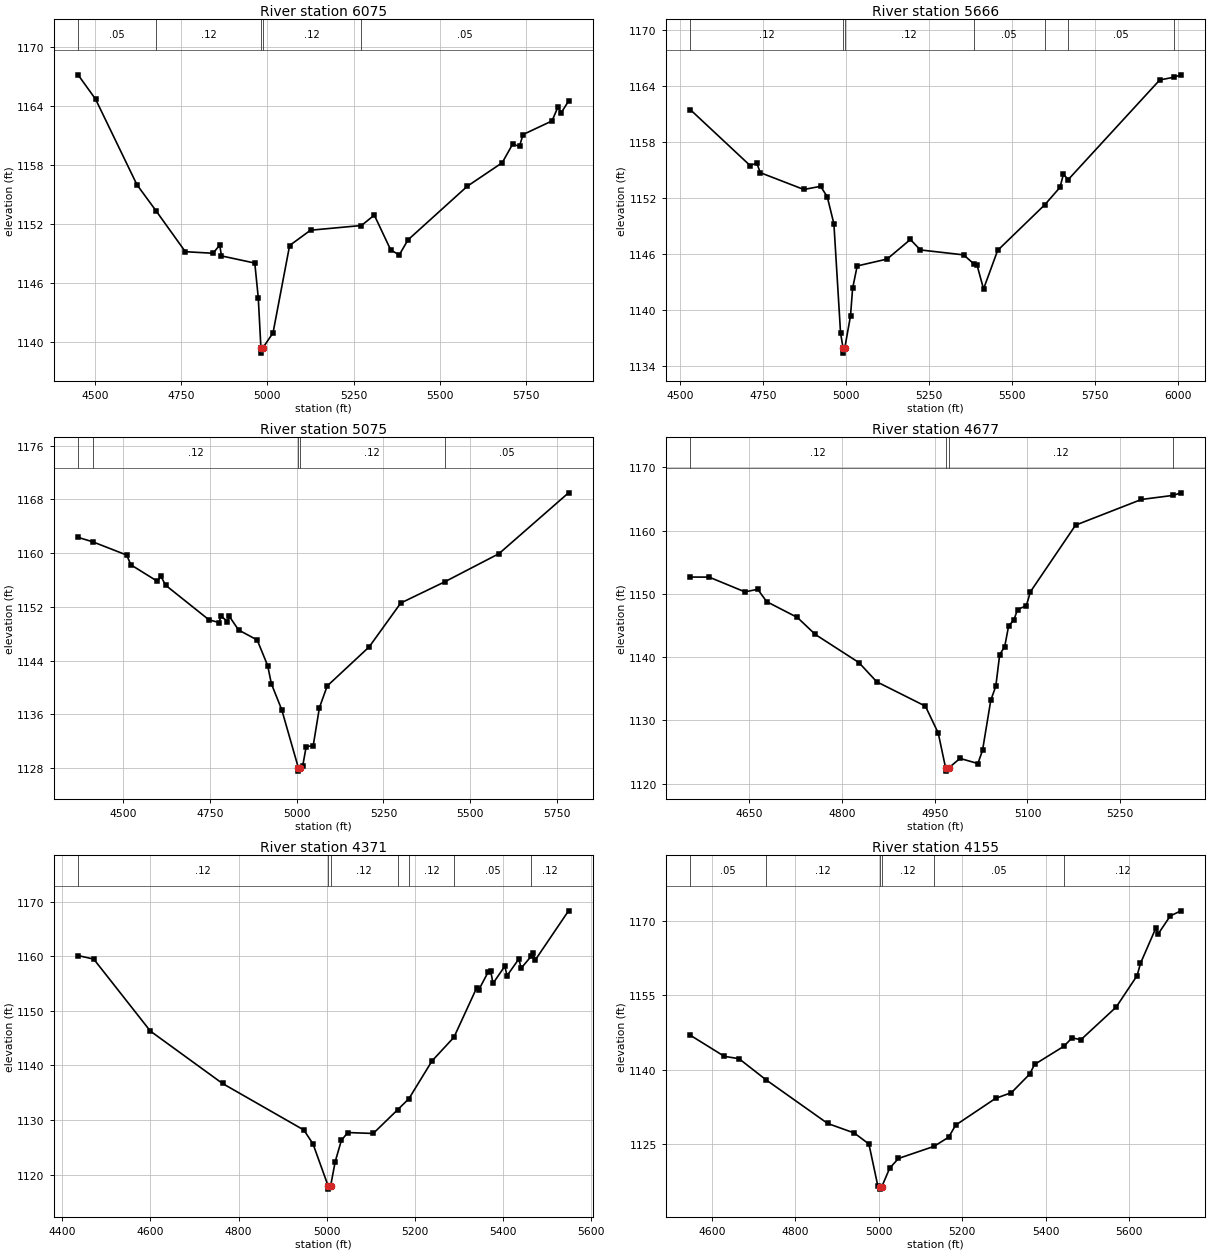
Type RM Length L Ch R = 1 ,6075    ,409,409,409
BEGIN DESCRIPTION:
JOHNSON CREEK 11.0
END DESCRIPTION:
XS GIS Cut Line= 3
      2822176.36     10171781.57      2821797.16     10171792.95
      2820764.89     10171651.37
#Sta/Elev= 30
  4451.7  1167.2  4502.4 1164.72  4622.4 1155.99  4677.4 1153.35  4762.5 1149.17
  4842.7 1149.01  4862.2 1149.84  4867.3 1148.74  4963.8 1148.01  4973.9 1144.47
  4981.6 1139.33  4981.9 1138.83  4986.4 1139.33  5016.6 1140.89  5064.7  1149.8
  5125.3 1151.36  5272.9 1151.84  5310.1  1152.9  5357.4 1149.37  5382.2 1148.83
  5407.9 1150.38  5579.5 1155.84  5680.8 1158.24  5710.7 1160.12  5730.9 1159.92
    5741 1161.11  5825.1  1162.5  5841.9 1163.89    5852 1163.35    5873 1164.52
#Mann= 5 ,-1 , 0
  4451.7     .05       0  4677.4     .12       0  4981.6     .07       0
  4986.4     .12       0  5272.9     .05       0
Bank Sta=4981.6,4986.4
XS Rating Curve= 0 ,0
Exp/Cntr=0.3,0.1

Type RM Length L Ch R = 1 ,5666    ,591,591,591
BEGIN DESCRIPTION:
JOHNSON CREEK 10.0
END DESCRIPTION:
XS GIS Cut Line= 3
      2822293.51     10171495.11      2821910.69     10171435.22
      2820822.18      10171359.7
#Sta/Elev= 30
  4530.2 1161.49  4710.2  1155.5  4730.4 1155.77  4740.6 1154.74  4872.1 1152.93
  4922.7 1153.27  4942.7 1152.15  4962.8 1149.24  4982.8 1137.55  4990.5 1135.86
  4990.8 1135.36  4995.3 1135.86  5012.9 1139.37  5019.1  1142.3    5033 1144.72
  5123.2 1145.46  5193.3 1147.56  5223.4 1146.44  5353.7 1145.91  5384.5 1144.95
  5393.8 1144.87  5413.9 1142.25  5456.4 1146.39  5598.5 1151.29  5644.4 1153.16
  5654.5 1154.55  5669.4    1154  5945.1 1164.69  5987.4 1164.98  6008.8 1165.24
#Mann= 7 ,-1 , 0
  4530.2     .12       0  4990.5     .07       0  4995.3     .12       0
  5384.5     .05       0  5598.5     .12       0  5669.4     .05       0
  5987.4     .12       0
Bank Sta=4990.5,4995.3
XS Rating Curve= 0 ,0
Exp/Cntr=0.3,0.1

Type RM Length L Ch R = 1 ,5075    ,398,398,398
BEGIN DESCRIPTION:
Mapping XS 33794eed
END DESCRIPTION:
XS GIS Cut Line= 3
      2822116.45     10171133.14      2821686.73     10170956.05
      2820746.58     10171086.26
#Sta/Elev= 30
  4369.9 1162.34  4412.5 1161.67  4510.1  1159.7  4522.1 1158.25  4598.2 1155.81
  4608.7 1156.55  4622.1 1155.22  4747.2 1150.06  4776.5 1149.65    4782 1150.64
  4800.5 1149.79  4805.9 1150.58  4832.5 1148.55  4886.2 1147.06  4916.5 1143.24
  4927.1 1140.55  4956.9 1136.69  5004.9 1128.03  5005.3 1127.53  5009.9 1128.03
  5017.5 1128.31  5027.5 1131.18  5047.7 1131.31  5065.6 1136.97  5088.1 1140.21
  5209.2 1146.04  5300.1 1152.56  5426.2  1155.7  5583.2 1159.91  5783.8 1168.97
#Mann= 5 ,-1 , 0
  4369.9     .05       0  4412.5     .12       0  5004.9     .07       0
  5009.9     .12       0  5426.2     .05       0
Bank Sta=5004.9,5009.9
XS Rating Curve= 0 ,0
Exp/Cntr=0.3,0.1

Type RM Length L Ch R = 1 ,4677    ,306,306,306
BEGIN DESCRIPTION:
JOHNSON CREEK 9.0
END DESCRIPTION:
XS GIS Cut Line= 3
      2821887.25     10170984.69      2821553.92     10170560.22
      2821349.43     10170410.08
#Sta/Elev= 30
  4554.8 1152.66  4585.1 1152.65  4642.9 1150.32  4663.7 1150.72  4678.2 1148.77
  4727.9 1146.27  4756.8 1143.59  4827.3 1139.15  4856.2 1136.11  4934.9 1132.26
  4955.7    1128  4967.6 1122.49    4968 1121.99  4972.6 1122.49  4990.9    1124
  5019.8 1123.19  5027.3 1125.26  5040.7  1133.2  5048.8  1135.4  5055.1 1140.41
  5063.2 1141.66  5069.6 1144.97  5077.7  1145.8    5084 1147.52  5098.3 1148.15
  5104.7 1150.32  5177.8 1160.86  5284.3 1164.92  5335.8 1165.57  5348.2 1165.97
#Mann= 4 ,-1 , 0
  4554.8     .12       0  4967.6     .07       0  4972.6     .12       0
  5335.8     .05       0
Bank Sta=4967.6,4972.6
XS Rating Curve= 0 ,0
Exp/Cntr=0.3,0.1

Type RM Length L Ch R = 1 ,4371    ,216,216,216
BEGIN DESCRIPTION:
JOHNSON CREEK 8.0
END DESCRIPTION:
XS GIS Cut Line= 3
      2822194.56     10170893.57      2821764.86     10170341.47
      2821371.66     10170213.87
#Sta/Elev= 30
  4435.9 1160.11  4471.5 1159.46    4600 1146.28  4763.7 1136.69  4948.3 1128.17
  4969.1 1125.61  5003.7 1117.85  5004.1 1117.35  5008.8 1117.85  5019.4 1122.39
  5033.4 1126.27  5047.8 1127.71  5105.7 1127.54  5161.4 1131.91  5186.5 1133.89
  5239.1 1140.82  5288.9 1145.16  5340.2 1154.16  5345.5 1153.88  5365.9 1157.01
  5372.2 1157.31  5377.4 1155.01  5404.2 1158.16  5409.4 1156.43  5436.1 1159.48
  5441.4  1157.8  5464.2 1159.99  5468.1 1160.59  5473.3 1159.29  5548.9  1168.3
#Mann= 7 ,-1 , 0
  4435.9     .12       0  5003.7     .07       0  5008.8     .12       0
  5161.4     .05       0  5186.5     .12       0  5288.9     .05       0
  5464.2     .12       0
Bank Sta=5003.7,5008.8
XS Rating Curve= 0 ,0
Exp/Cntr=0.3,0.1

Type RM Length L Ch R = 1 ,4155    ,314,314,314
BEGIN DESCRIPTION:
JOHNSON CREEK 7.0
END DESCRIPTION:
XS GIS Cut Line= 3
       2822348.2     10170625.33      2821879.44     10170195.63
      2821350.84     10170086.27
#Sta/Elev= 30
  4548.6 1146.93  4629.9 1142.69  4665.1 1142.22  4729.6 1137.98  4877.6 1129.17
  4941.3 1127.25  4976.5 1125.03  4998.1 1116.48  5002.3 1116.44  5002.7 1115.94
  5007.4 1116.44  5026.4 1120.18  5047.4 1122.12  5132.3 1124.55  5167.6  1126.4
  5184.5 1128.84  5280.2 1134.23  5318.2 1135.38  5361.9 1139.12  5373.5 1141.06
  5443.8 1144.72  5463.7 1146.43  5484.5 1146.03  5569.2 1152.62  5619.4 1158.96
  5627.4 1161.42  5664.5 1168.58  5669.6 1167.32  5698.9 1170.98  5724.3 1172.01
#Mann= 6 ,-1 , 0
  4548.6     .05       0  4729.6     .12       0  5002.3     .07       0
  5007.4     .12       0  5132.3     .05       0  5443.8     .12       0
Bank Sta=5002.3,5007.4
XS Rating Curve= 0 ,0
Exp/Cntr=0.3,0.1

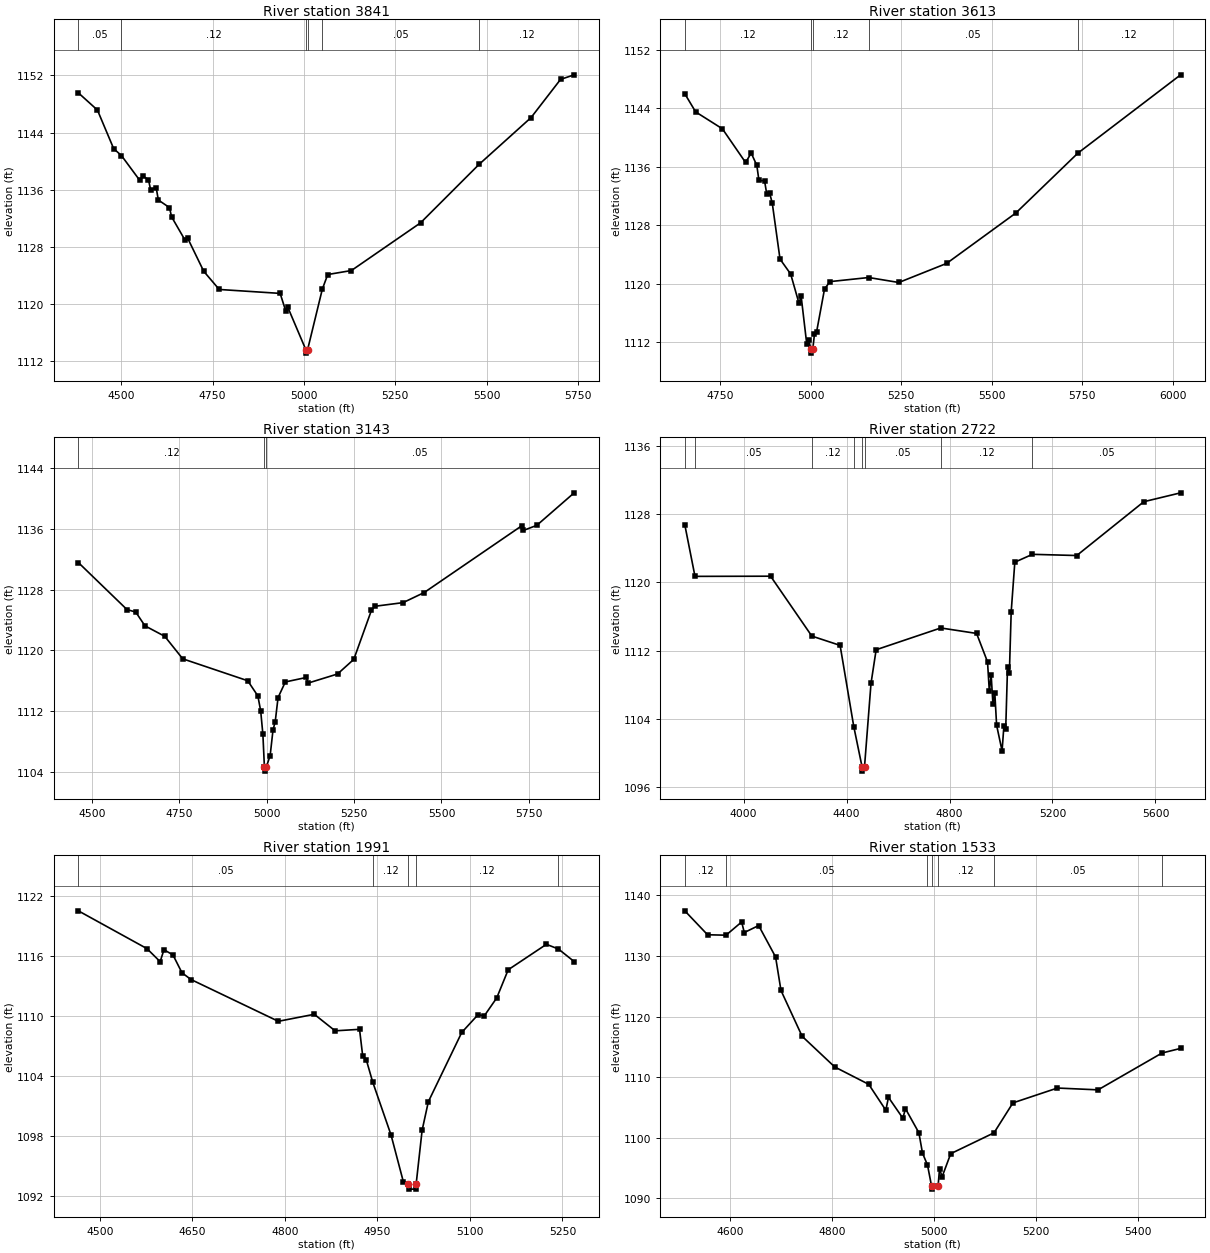
Type RM Length L Ch R = 1 ,3841    ,228,228,228
BEGIN DESCRIPTION:
JOHNSON CREEK 6.0
END DESCRIPTION:
XS GIS Cut Line= 3
      2822387.24     10170544.57      2821985.89     10169917.96
      2821378.79     10169841.71
#Sta/Elev= 30
    4383 1149.57  4435.2 1147.16  4479.7 1141.75  4500.9 1140.79    4551 1137.32
  4559.5 1137.91  4574.7 1137.43  4580.6 1136.03  4595.8 1136.32  4601.8 1134.57
  4632.2 1133.51  4638.1 1132.21  4674.5 1128.98  4681.6 1129.27    4726 1124.59
  4768.3 1122.05  4934.9  1121.5  4950.1 1119.06    4956 1119.54    5005 1113.64
  5005.4 1113.14  5010.1 1113.64  5050.3  1122.1  5065.1 1124.14  5129.8  1124.7
  5318.8 1131.37  5478.6 1139.54  5621.2 1146.11  5701.8 1151.45    5739 1152.09
#Mann= 6 ,-1 , 0
    4383     .05       0  4500.9     .12       0    5005     .07       0
  5010.1     .12       0  5050.3     .05       0  5478.6     .12       0
Bank Sta=5005,5010.1
XS Rating Curve= 0 ,0
Exp/Cntr=0.3,0.1

Type RM Length L Ch R = 1 ,3613    ,470,470,470
BEGIN DESCRIPTION:
JOHNSON CREEK 5.0
END DESCRIPTION:
XS GIS Cut Line= 3
      2822426.34     10170393.58       2822088.1      10169832.4
      2821390.26      10169680.1
#Sta/Elev= 30
    4652 1145.96    4682 1143.48  4755.8 1141.17  4819.9 1136.56  4835.4 1137.85
  4850.9 1136.17  4856.8  1134.1  4872.3 1134.06  4878.1 1132.32  4886.1 1132.44
  4893.7 1130.96    4915 1123.35  4944.4 1121.31  4967.4 1117.31  4973.3 1118.29
  4988.8 1111.75  4994.6 1112.23  5000.3 1110.99  5000.7 1110.49  5005.4 1110.99
  5010.2 1113.11    5016 1113.39  5037.9 1119.25  5052.9 1120.27    5160 1120.83
  5243.1 1120.15  5375.2 1122.76  5566.3 1129.65  5737.7 1137.84  6021.5 1148.55
#Mann= 5 ,-1 , 0
    4652     .12       0  5000.3     .07       0  5005.4     .12       0
    5160     .05       0  5737.7     .12       0
Bank Sta=5000.3,5005.4
XS Rating Curve= 0 ,0
Exp/Cntr=0.3,0.1

Type RM Length L Ch R = 1 ,3143    ,421,421,421
BEGIN DESCRIPTION:
JOHNSON CREEK 4.0
END DESCRIPTION:
XS GIS Cut Line= 4
      2822477.42     10170174.37      2822387.25     10169713.86
      2822254.44      10169609.7      2821479.51     10169521.28
#Sta/Elev= 30
  4461.4 1131.56  4600.4 1125.36  4625.7 1125.02  4651.9 1123.21  4708.5 1121.83
    4760 1118.86  4945.8 1115.97  4974.8 1113.97  4982.9    1112  4989.2  1108.9
  4993.6 1104.55    4994 1104.05  4998.7 1104.55    5010 1106.11  5018.1 1109.46
  5024.5 1110.58  5032.6 1113.75  5053.4 1115.81  5113.3  1116.4  5118.4 1115.66
  5202.7 1116.86  5249.2 1118.79  5299.5 1125.24  5309.6 1125.79  5390.1 1126.27
  5450.5  1127.6  5729.1 1136.39  5734.1 1135.79  5772.5 1136.46  5879.4 1140.75
#Mann= 3 ,-1 , 0
  4461.4     .12       0  4993.6     .07       0  4998.7     .05       0
Bank Sta=4993.6,4998.7
XS Rating Curve= 0 ,0
Exp/Cntr=0.3,0.1

Type RM Length L Ch R = 1 ,2722    ,731,731,731
BEGIN DESCRIPTION:
Mapping XS c6b3c9db
END DESCRIPTION:
XS GIS Cut Line= 4
      2823368.99      10169549.8      2822535.69     10169557.61
      2822202.36     10169221.67      2821595.59     10169096.67
#Sta/Elev= 30
  3771.7 1126.72  3811.3 1120.68    4105  1120.7  4265.1 1113.69    4375  1112.6
  4428.1  1103.1  4460.3 1098.38  4460.8 1097.88  4469.8 1098.38    4495 1108.14
    4515 1112.09  4766.1 1114.64  4905.2    1114  4947.7 1110.67  4954.7 1107.21
  4961.8 1109.13  4968.8 1105.68  4975.9 1107.07    4983 1103.25  5004.2 1100.25
  5011.3 1103.17  5018.4 1102.86  5025.4 1110.05  5032.5 1109.31  5039.6 1116.52
  5053.7 1122.34  5122.2 1123.26  5294.3 1123.12  5554.8 1129.42  5697.8 1130.46
#Mann= 8 ,-1 , 0
  3771.7     .12       0  3811.3     .05       0  4265.1     .12       0
  4428.1     .05       0  4460.3     .07       0  4469.8     .05       0
  4766.1     .12       0  5122.2     .05       0
Bank Sta=4460.3,4469.8
XS Rating Curve= 0 ,0
Exp/Cntr=0.3,0.1

Type RM Length L Ch R = 1 ,1991    ,458,458,458
BEGIN DESCRIPTION:
JOHNSON CREEK 3.0
END DESCRIPTION:
XS GIS Cut Line= 3
      2823121.85     10169552.15      2822889.86     10169242.51
      2822837.78     10168828.48
#Sta/Elev= 30
  4464.9 1120.49  4576.2 1116.72  4597.6 1115.42  4603.8 1116.61  4618.4 1116.09
    4633 1114.31  4647.6 1113.64  4789.3 1109.47  4847.6 1110.17  4881.4 1108.52
    4921 1108.67  4926.1 1106.03  4931.8 1105.66  4942.2 1103.44  4972.1 1098.13
  4992.3 1093.41    5000 1093.23  5000.5 1092.73  5012.3 1092.73  5012.8 1093.23
  5022.5  1098.6  5032.6 1101.45  5086.8 1108.36  5113.2 1110.13  5123.3 1110.01
  5143.5  1111.8  5162.1 1114.61  5224.1 1117.15  5243.6 1116.68  5269.1 1115.43
#Mann= 5 ,-1 , 0
  4464.9     .05       0  4942.2     .12       0    5000     .07       0
  5012.8     .12       0  5243.6     .05       0
Bank Sta=5000,5012.8
XS Rating Curve= 0 ,0
Exp/Cntr=0.3,0.1

Type RM Length L Ch R = 1 ,1533    ,553,553,553
BEGIN DESCRIPTION:
JOHNSON CREEK 2.0
END DESCRIPTION:
XS GIS Cut Line= 3
      2823452.36     10169594.09      2823270.07     10168971.67
      2822991.38     10168804.98
#Sta/Elev= 30
  4510.6 1137.46  4555.3 1133.51  4591.5 1133.44  4622.2 1135.62  4627.4 1133.88
  4655.6 1135.03  4688.8 1129.85  4699.4 1124.32  4740.9 1116.76  4804.9  1111.7
  4871.7 1108.83  4905.2 1104.56  4910.4 1106.68  4938.6 1103.25  4943.8 1104.81
  4970.1 1100.84  4977.2 1097.48    4987 1095.52    4995 1092.04  4995.5 1091.54
  5007.8 1092.04  5010.6 1094.84  5015.8  1093.6  5032.6 1097.39  5117.6 1100.83
  5154.7 1105.77    5242 1108.22  5321.8 1107.92  5447.4    1114  5483.9 1114.76
#Mann= 7 ,-1 , 0
  4510.6     .12       0  4591.5     .05       0    4987     .12       0
    4995     .07       0  5007.8     .12       0  5117.6     .05       0
  5447.4     .12       0
Bank Sta=4995,5007.8
XS Rating Curve= 0 ,0
Exp/Cntr=0.3,0.1