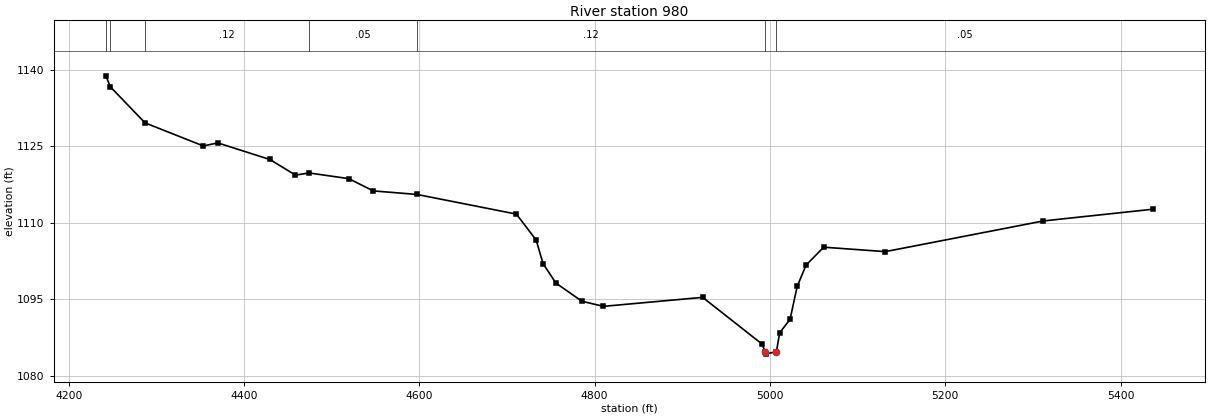
HEC-RAS study JOHNSON CREEK.prj: JOHNSON CREEK Base Level Engineering

--- JOHNSON CREEK.g01 (geometry) --- (continued)

Type RM Length L Ch R = 1 ,980     ,0,0,0
BEGIN DESCRIPTION:
JOHNSON CREEK 1.0
END DESCRIPTION:
XS GIS Cut Line= 3
      2824191.94     10168937.82      2823702.36     10168685.22
      2823061.76     10168750.32
#Sta/Elev= 30
  4242.3 1138.78  4247.3 1136.64    4287 1129.56  4353.5 1125.04    4370 1125.64
  4429.4 1122.39  4458.6 1119.33  4474.2 1119.75  4519.4 1118.64  4547.3 1116.24
  4597.3 1115.54  4710.7 1111.69  4733.2 1106.61  4741.1    1102  4755.7 1098.19
  4785.4 1094.62    4810 1093.62  4923.2 1095.38  4990.9 1086.24  4994.5 1084.76
    4995 1084.26  5007.4 1084.76    5011 1088.42  5022.9 1091.08  5031.1 1097.55
  5041.2  1101.7  5061.3 1105.21  5131.6 1104.34  5311.9 1110.35  5437.1 1112.65
#Mann= 7 ,-1 , 0
  4242.3     .12       0  4247.3     .05       0    4287     .12       0
  4474.2     .05       0  4597.3     .12       0  4994.5     .07       0
  5007.4     .05       0
Bank Sta=4994.5,5007.4
XS Rating Curve= 0 ,0
Exp/Cntr=0.3,0.1

Chan Stop Cuts=-1
Use User Specified Reach Order=0
Composite Channel Slope=5