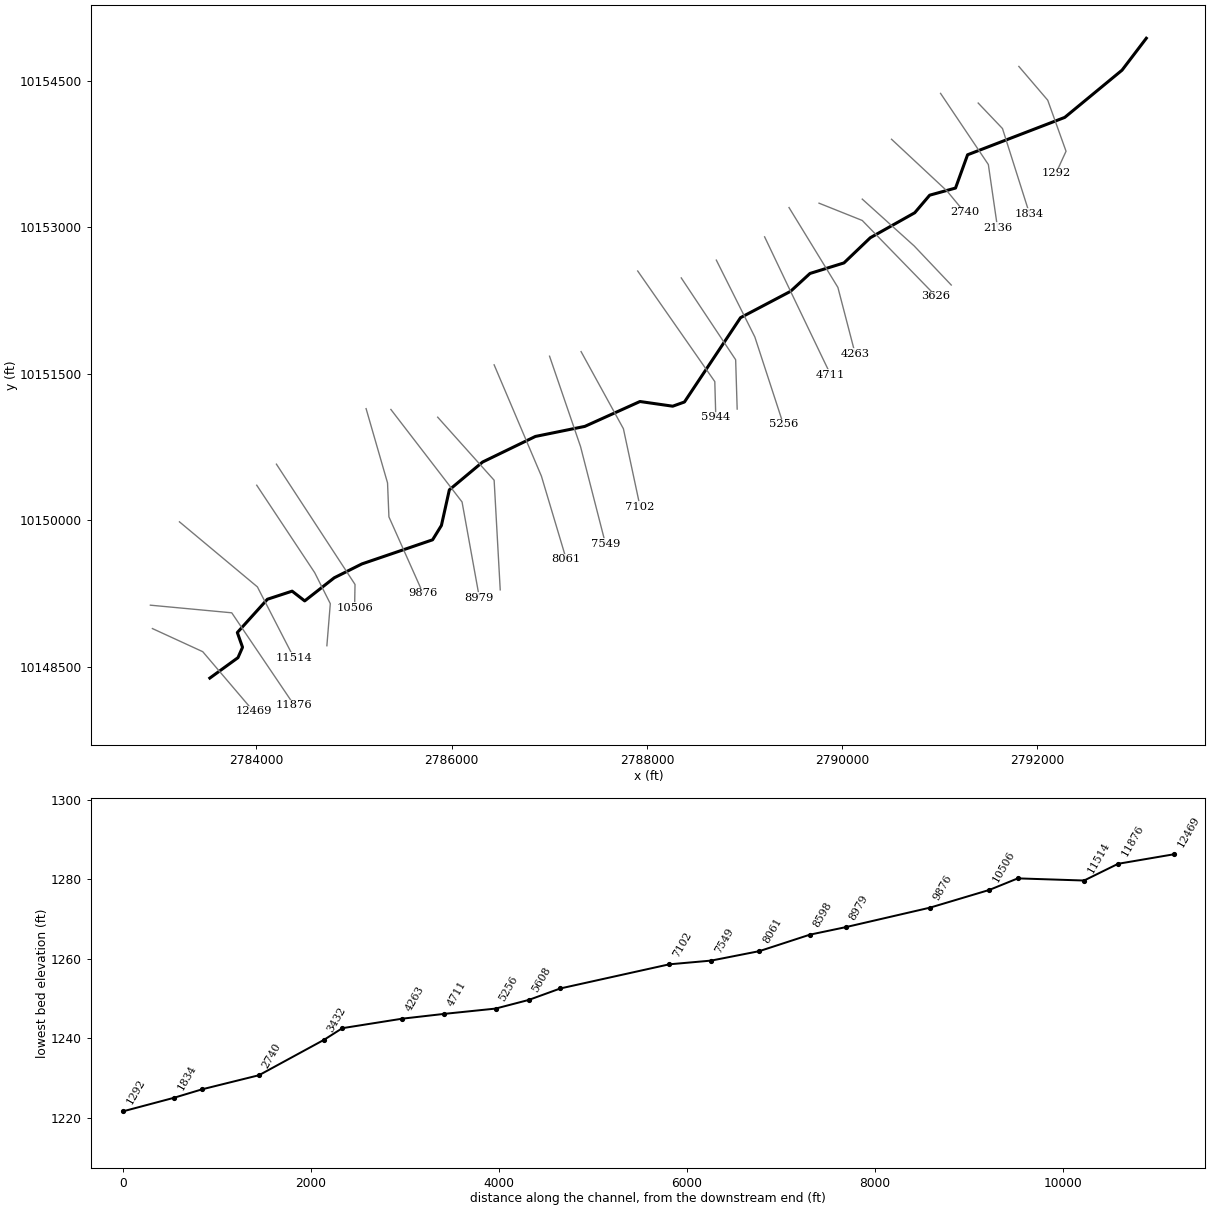
--- KEENER BRANCH.prj (project) ---

Proj Title=KEENER BRANCH Base Level Engineering
Current Plan=p01
Default Exp/Contr=0.3,0.1
English Units
Geom File=g01
Flow File=f01
Plan File=p01
BEGIN DESCRIPTION:
KEENER BRANCH
END DESCRIPTION:

--- KEENER BRANCH.p01 (plan) ---

Plan Title=Multiple Run
Short Identifier=Multiple
Geom File=g01
Flow File=f01
Subcritical Flow
K Sum by GR= 0
Std Step Tol= 0.01
Critical Tol= 0.01
Num of Std Step Trials= 20
Max Error Tol= 0.3
Flow Tol Ratio= 0.001
Split Flow NTrial= 30
Split Flow Tol= 0.02
Split Flow Ratio= 0.02
Log Output Level= 0
Friction Slope Method= 1
Unsteady Friction Slope Method= 2
Unsteady Bridges Friction Slope Method= 1
Parabolic Critical Depth
Global Vel Dist=  1 , 1 , 1
Global Log Level= 0
CheckData=True
Encroach Param= -1, 0, 0, 0
BEGIN DESCRIPTION:
Multiple Run
END DESCRIPTION:

--- KEENER BRANCH.f01 (steady flow) ---

Flow Title=Multiple
Number of Profiles=7
Profile Names=10-year,25-year,50-year,1pct_min,100-year,1pct_plu,500-year
River Rch & RM= KEENER BRANCH,Reach-1,12469
    1150    1990    5015    3781    7442   14651   11012
River Rch & RM= KEENER BRANCH,Reach-1,9876
    1662    2935    7585    5692   11371   22718   16696
River Rch & RM= KEENER BRANCH,Reach-1,4711
    1786    3172    8048    5958   12073   24461   17697
River Rch & RM= KEENER BRANCH,Reach-1,2136
    2018    3608    9223    6819   13882   28257   20294
Boundary for River Rch & Prof#=KEENER BRANCH,Reach-1,1
Up Type=0
Dn Type=3
Dn Slope=0.005
Boundary for River Rch & Prof#=KEENER BRANCH,Reach-1,2
Up Type=0
Dn Type=3
Dn Slope=0.005
Boundary for River Rch & Prof#=KEENER BRANCH,Reach-1,3
Up Type=0
Dn Type=3
Dn Slope=0.005
Boundary for River Rch & Prof#=KEENER BRANCH,Reach-1,4
Up Type=0
Dn Type=3
Dn Slope=0.005
Boundary for River Rch & Prof#=KEENER BRANCH,Reach-1,5
Up Type=0
Dn Type=3
Dn Slope=0.005
Boundary for River Rch & Prof#=KEENER BRANCH,Reach-1,6
Up Type=0
Dn Type=3
Dn Slope=0.005
Boundary for River Rch & Prof#=KEENER BRANCH,Reach-1,7
Up Type=0
Dn Type=3
Dn Slope=0.005

--- KEENER BRANCH.g01 (geometry) ---

Geom Title=Existing Conditions

River Reach=KEENER BRANCH,Reach-1
Reach XY= 30
      2783522.74     10148382.20      2783810.93     10148591.40
      2783857.75     10148698.00      2783804.50     10148849.00
      2784112.50     10149190.00      2784365.75     10149273.00
      2784494.50     10149173.00      2784797.25     10149410.00
      2785080.50     10149552.00      2785804.50     10149799.00
      2785895.00     10149946.00      2785976.25     10150311.00
      2786317.00     10150596.00      2786857.50     10150858.00
      2787363.75     10150961.00      2787928.75     10151216.00
      2788264.25     10151168.00      2788384.50     10151211.00
      2788959.00     10152075.00      2789471.50     10152345.00
      2789670.50     10152528.00      2790018.50     10152636.00
      2790288.25     10152894.00      2790743.50     10153150.00
      2790896.50     10153330.00      2791161.25     10153403.00
      2791284.75     10153744.00      2792280.25     10154127.00
      2792867.00     10154611.00      2793115.75     10154938.00

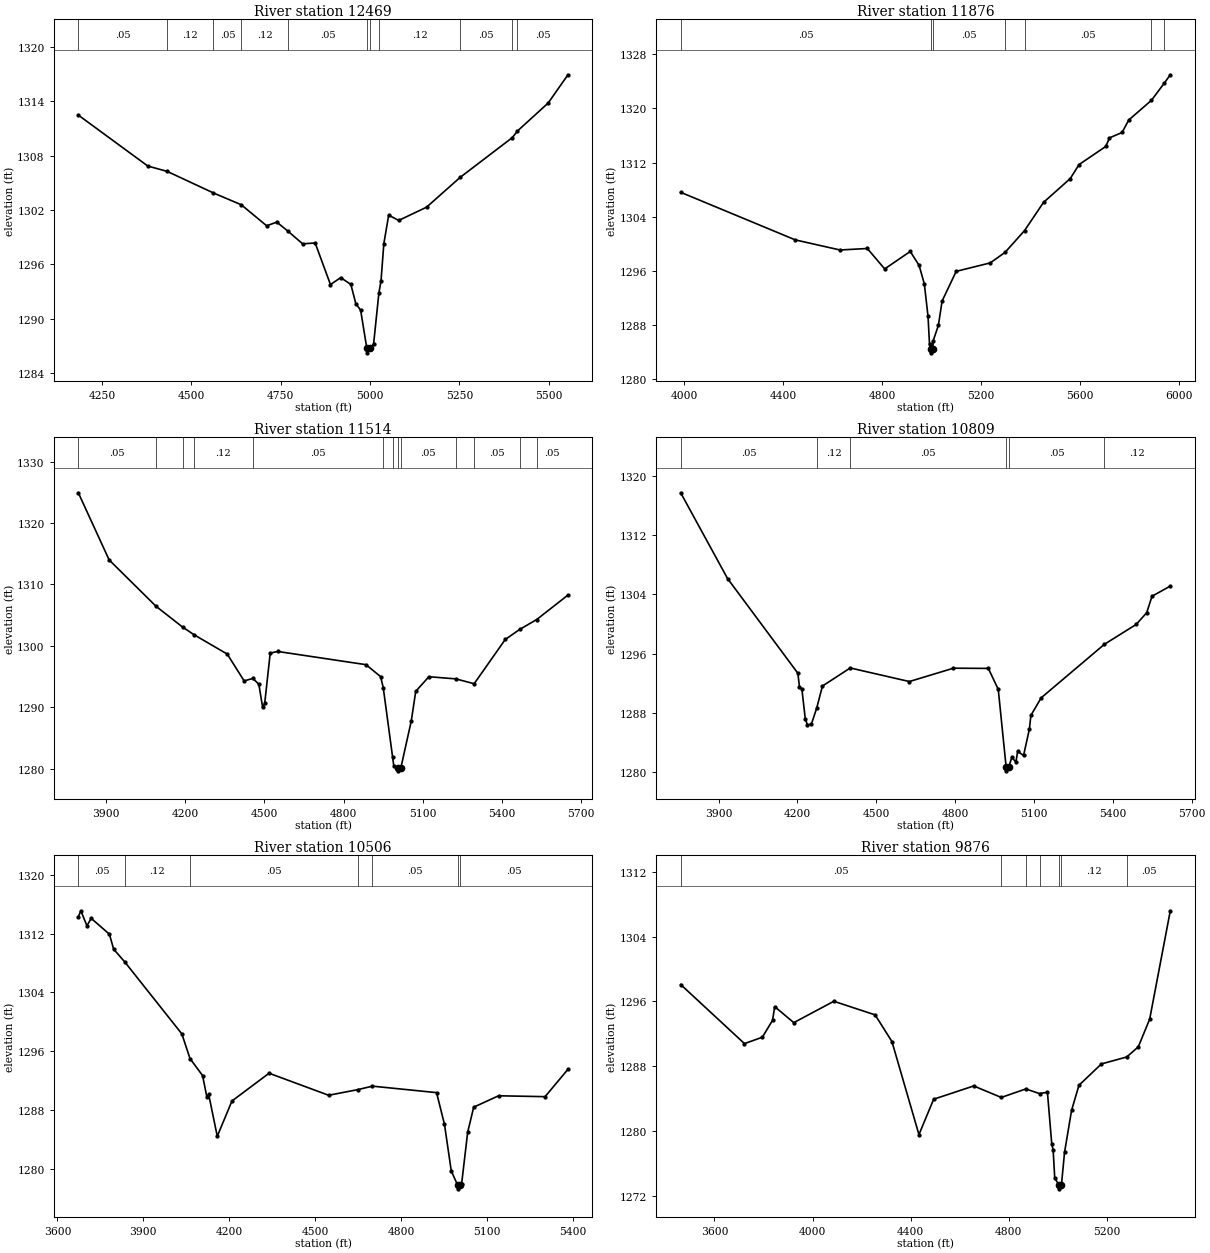
Type RM Length L Ch R = 1,12469,593,593,593
BEGIN DESCRIPTION:
KEENER BRANCH 23.0
END DESCRIPTION:
XS GIS Cut Line= 3
      2782934.64     10148889.66      2783450.25     10148652.69
      2783970.91     10148040.92
#Sta/Elev= 30
  4183.3 1312.48  4377.8 1306.86  4432.1 1306.27  4561.6 1303.89  4639.8 1302.58
  4710.5 1300.27  4739.0 1300.67  4770.9 1299.65  4811.2 1298.28  4846.4 1298.37
  4889.2 1293.78  4917.8 1294.55  4946.3 1293.80  4960.3 1291.66  4973.7 1290.96
  4991.0 1286.75  4991.5 1286.25  5000.5 1286.75  5010.0 1287.23  5024.8 1292.86
  5030.8 1294.22  5038.6 1298.28  5052.2 1301.44  5080.3 1300.86  5158.2 1302.32
  5252.3 1305.61  5398.4 1310.00  5412.8 1310.73  5498.7 1313.81  5554.1 1316.93
#Mann=11,-1,0
  4183.3    0.05       0  4432.1    0.12       0  4561.6    0.05       0
  4639.8    0.12       0  4770.9    0.05       0  4991.0    0.05       0
  5000.5    0.05       0  5024.8    0.12       0  5252.3    0.05       0
  5398.4    0.12       0  5412.8    0.05       0
Bank Sta=4991,5000.5
Exp/Cntr=0.3,0.1

Type RM Length L Ch R = 1,11876,362,362,362
BEGIN DESCRIPTION:
Mapping XS 177c2826
END DESCRIPTION:
XS GIS Cut Line= 3
      2782913.76     10149129.26      2783747.13     10149051.13
      2784387.74     10148103.23
#Sta/Elev= 30
  3984.9 1307.60  4448.9 1300.56  4629.6 1299.07  4740.1 1299.29  4810.4 1296.27
  4913.8 1298.85  4949.8 1296.78  4970.8 1294.05  4985.7 1289.28  4991.8 1285.10
  4995.8 1284.36  4996.3 1283.86  5005.4 1284.36  5006.7 1285.65  5027.7 1287.93
  5042.7 1291.52  5099.7 1295.91  5237.5 1297.16  5297.3 1298.71  5376.3 1301.94
  5453.3 1306.12  5561.2 1309.63  5597.1 1311.71  5705.0 1314.38  5720.0 1315.65
  5770.9 1316.45  5797.9 1318.29  5889.6 1321.20  5941.5 1323.73  5966.0 1324.98
#Mann=7,-1,0
  3984.9    0.05       0  4995.8    0.05       0  5005.4    0.05       0
  5297.3    0.12       0  5376.3    0.05       0  5889.6    0.12       0
  5941.5    0.05       0
Bank Sta=4995.8,5005.4
Exp/Cntr=0.3,0.1

Type RM Length L Ch R = 1,11514,705,705,705
BEGIN DESCRIPTION:
KEENER BRANCH 22.0
END DESCRIPTION:
XS GIS Cut Line= 3
      2783211.51     10149983.20      2784010.09     10149316.56
      2784382.92     10148591.79
#Sta/Elev= 30
  3794.6 1324.91  3911.3 1313.98  4089.4 1306.42  4189.4 1303.06  4232.4 1301.82
  4359.0 1298.65  4422.8 1294.29  4456.2 1294.69  4478.7 1293.73  4493.0 1289.97
  4500.8 1290.62  4521.7 1298.82  4550.3 1299.08  4884.6 1296.93  4939.9 1294.99
  4950.0 1293.20  4985.2 1281.97  4989.9 1280.47  5007.2 1280.15  5007.7 1279.65
  5016.8 1280.15  5056.4 1287.80  5073.0 1292.58  5122.9 1294.97  5224.9 1294.62
  5294.5 1293.83  5412.3 1301.03  5466.8 1302.66  5531.6 1304.28  5649.9 1308.26
#Mann=13,-1,0
  3794.6    0.05       0  4089.4    0.12       0  4189.4    0.05       0
  4232.4    0.12       0  4456.2    0.05       0  4950.0    0.12       0
  4985.2    0.05       0  5007.2    0.05       0  5016.8    0.05       0
  5224.9    0.12       0  5294.5    0.05       0  5466.8    0.12       0
  5531.6    0.05       0
Bank Sta=5007.2,5016.8
Exp/Cntr=0.3,0.1

Type RM Length L Ch R = 1,10809,303,303,303
BEGIN DESCRIPTION:
KEENER BRANCH 21.0
END DESCRIPTION:
XS GIS Cut Line= 4
      2784003.16     10150358.21      2784596.90     10149462.40
      2784756.79     10149144.73      2784721.71     10148713.71
#Sta/Elev= 30
  3755.9 1317.68  3934.2 1306.12  4201.9 1293.34  4207.9 1291.47  4217.0 1291.22
  4229.9 1287.23  4238.0 1286.38  4253.1 1286.48  4273.8 1288.69  4295.2 1291.62
  4401.0 1294.06  4626.0 1292.23  4793.8 1294.03  4926.5 1294.00  4964.2 1291.17
  4994.2 1280.69  4994.7 1280.19  5003.9 1280.69  5015.8 1282.01  5031.3 1281.37
  5038.1 1282.82  5060.4 1282.26  5082.7 1285.83  5088.3 1287.66  5127.3 1290.03
  5368.0 1297.25  5488.9 1299.93  5529.0 1301.51  5549.1 1303.73  5618.7 1305.10
#Mann=6,-1,0
  3755.9    0.05       0  4273.8    0.12       0  4401.0    0.05       0
  4994.2    0.05       0  5003.9    0.05       0  5368.0    0.12       0
Bank Sta=4994.2,5003.9
Exp/Cntr=0.3,0.1

Type RM Length L Ch R = 1,10506,630,630,630
BEGIN DESCRIPTION:
KEENER BRANCH 20.0
END DESCRIPTION:
XS GIS Cut Line= 3
      2784204.87     10150574.02      2785009.96     10149341.74
      2785005.68     10149103.15
#Sta/Elev= 30
  3673.1 1314.30  3681.9 1315.11  3703.0 1313.07  3718.1 1314.08  3781.7 1311.92
  3796.5 1309.88  3834.7 1308.18  4034.8 1298.36  4063.1 1295.01  4107.2 1292.69
  4122.3 1289.74  4128.3 1290.16  4158.5 1284.43  4209.8 1289.23  4339.5 1293.01
  4547.6 1290.01  4648.6 1290.77  4700.8 1291.25  4924.7 1290.37  4952.3 1286.06
  4976.0 1279.73  4998.2 1277.78  4998.7 1277.28  5007.9 1277.78  5012.0 1277.88
  5033.3 1284.97  5054.4 1288.39  5141.3 1289.94  5303.7 1289.82  5383.7 1293.54
#Mann=7,-1,0
  3673.1    0.05       0  3834.7    0.12       0  4063.1    0.05       0
  4648.6    0.12       0  4700.8    0.05       0  4998.2    0.05       0
  5007.9    0.05       0
Bank Sta=4998.2,5007.9
Exp/Cntr=0.3,0.1

Type RM Length L Ch R = 1,9876,897,897,897
BEGIN DESCRIPTION:
KEENER BRANCH 19.0
END DESCRIPTION:
XS GIS Cut Line= 4
      2785123.47     10151142.88      2785343.13     10150381.54
      2785357.30     10150033.90      2785705.68     10149253.12
#Sta/Elev= 30
  3462.6 1298.07  3722.6 1290.77  3795.4 1291.56  3837.0 1293.65  3845.8 1295.34
  3923.5 1293.36  4086.8 1296.00  4255.0 1294.32  4323.5 1291.03  4433.6 1279.53
  4493.6 1283.90  4656.7 1285.54  4769.2 1284.12  4868.9 1285.17  4924.9 1284.60
  4957.2 1284.76  4975.0 1278.33  4980.5 1277.63  4987.0 1274.16  5003.9 1273.33
  5004.4 1272.83  5014.4 1273.33  5026.9 1277.33  5055.6 1282.52  5085.6 1285.62
  5177.2 1288.26  5280.4 1289.12  5327.5 1290.37  5373.9 1293.79  5457.9 1307.18
#Mann=7,-1,0
  3462.6    0.05       0  4769.2    0.12       0  4868.9    0.05       0
  4924.9    0.12       0  5003.9    0.07       0  5014.4    0.12       0
  5280.4    0.05       0
Bank Sta=5003.9,5014.4
Exp/Cntr=0.3,0.1

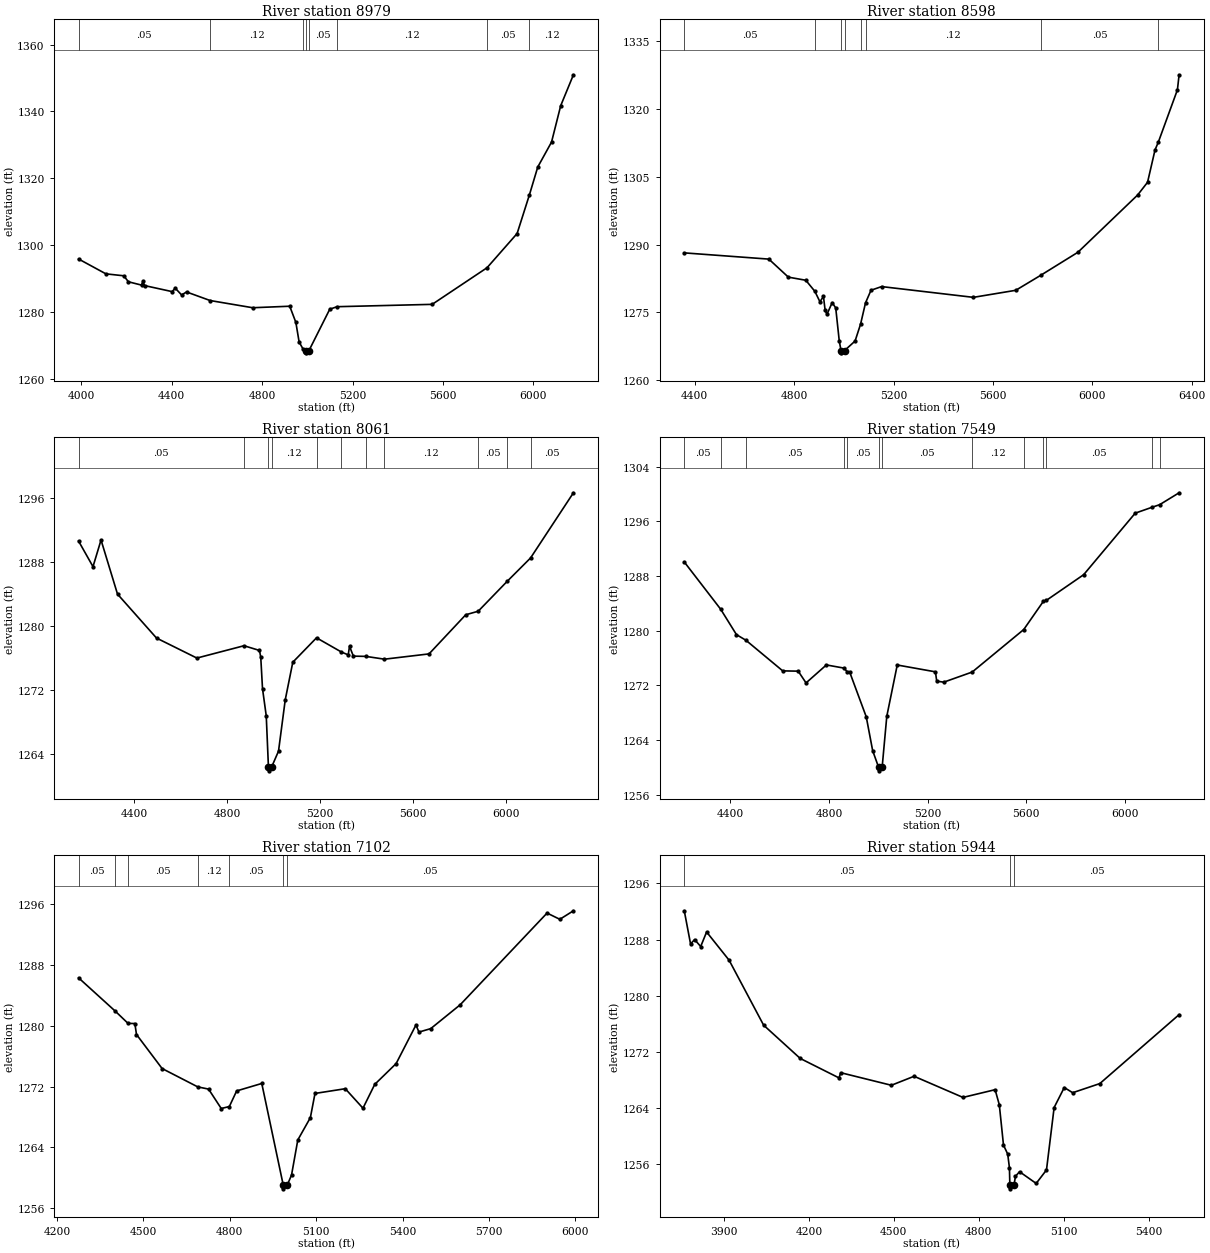
Type RM Length L Ch R = 1,8979,381,381,381
BEGIN DESCRIPTION:
KEENER BRANCH 18.0
END DESCRIPTION:
XS GIS Cut Line= 3
      2785377.33     10151134.47      2786106.50     10150186.54
      2786283.52     10149207.75
#Sta/Elev= 30
  3987.4 1295.94  4108.3 1291.51  4187.2 1290.93  4208.0 1289.14  4266.0 1288.15
  4272.3 1289.35  4279.3 1288.01  4401.0 1286.21  4415.5 1287.21  4443.3 1285.22
  4465.4 1286.10  4569.7 1283.54  4758.1 1281.39  4922.1 1281.84  4949.2 1277.02
  4963.7 1271.15  4980.3 1269.15  4992.0 1268.42  4992.5 1267.92  5006.0 1268.42
  5099.3 1280.95  5131.9 1281.70  5552.7 1282.40  5795.5 1293.33  5928.7 1303.55
  5983.5 1315.17  6020.1 1323.41  6081.1 1330.86  6121.7 1341.73  6178.0 1350.96
#Mann=8,-1,0
  3987.4    0.05       0  4569.7    0.12       0  4980.3    0.05       0
  4992.0    0.05       0  5006.0    0.05       0  5131.9    0.12       0
  5795.5    0.05       0  5983.5    0.12       0
Bank Sta=4992,5006
Exp/Cntr=0.3,0.1

Type RM Length L Ch R = 1,8598,537,537,537
BEGIN DESCRIPTION:
KEENER BRANCH 17.0
END DESCRIPTION:
XS GIS Cut Line= 3
      2785856.87     10151055.34      2786435.01     10150409.49
      2786497.41     10149286.34
#Sta/Elev= 30
  4357.6 1288.15  4698.0 1286.77  4776.5 1282.78  4846.8 1282.09  4883.2 1279.64
  4903.6 1277.33  4917.8 1278.51  4924.5 1275.46  4932.0 1274.56  4953.0 1277.15
  4967.2 1275.96  4981.4 1268.67  4988.5 1266.53  4989.0 1266.03  5002.6 1266.53
  5045.1 1268.64  5067.3 1272.40  5087.1 1277.09  5109.2 1279.88  5151.9 1280.69
  5521.3 1278.31  5691.9 1279.87  5791.8 1283.17  5941.9 1288.28  6182.3 1300.95
  6222.3 1303.77  6252.4 1310.94  6265.6 1312.64  6342.5 1324.23  6349.3 1327.56
#Mann=8,-1,0
  4357.6    0.05       0  4883.2    0.12       0  4988.5    0.07       0
  5002.6    0.12       0  5067.3    0.05       0  5087.1    0.12       0
  5791.8    0.05       0  6265.6    0.12       0
Bank Sta=4988.5,5002.6
Exp/Cntr=0.3,0.1

Type RM Length L Ch R = 1,8061,512,512,512
BEGIN DESCRIPTION:
KEENER BRANCH 16.0
END DESCRIPTION:
XS GIS Cut Line= 3
      2786435.00     10151591.82      2786919.39     10150451.15
      2787174.42     10149597.59
#Sta/Elev= 30
  4161.6 1290.59  4223.6 1287.40  4258.2 1290.73  4329.1 1283.97  4497.0 1278.48
  4670.8 1275.98  4873.7 1277.52  4940.3 1276.93  4945.8 1276.07  4953.3 1272.16
  4969.4 1268.76  4978.8 1262.39  4979.3 1261.89  4992.9 1262.39  5022.2 1264.35
  5051.2 1270.77  5083.7 1275.46  5185.8 1278.51  5293.3 1276.73  5322.3 1276.38
  5327.8 1277.46  5344.4 1276.22  5398.1 1276.19  5478.4 1275.84  5670.2 1276.50
  5828.2 1281.39  5881.8 1281.83  6006.0 1285.55  6107.3 1288.49  6291.7 1296.63
#Mann=11,-1,0
  4161.6    0.05       0  4873.7    0.12       0  4978.8    0.07       0
  4992.9    0.12       0  5185.8    0.05       0  5293.3    0.12       0
  5398.1    0.05       0  5478.4    0.12       0  5881.8    0.05       0
  6006.0    0.12       0  6107.3    0.05       0
Bank Sta=4978.8,4992.9
Exp/Cntr=0.3,0.1

Type RM Length L Ch R = 1,7549,447,447,447
BEGIN DESCRIPTION:
KEENER BRANCH 15.0
END DESCRIPTION:
XS GIS Cut Line= 3
      2787002.73     10151680.29      2787320.43     10150753.24
      2787575.64     10149758.43
#Sta/Elev= 30
  4213.3 1290.06  4360.9 1283.15  4425.0 1279.43  4463.3 1278.61  4612.6 1274.13
  4675.4 1274.09  4707.2 1272.37  4789.7 1275.00  4862.2 1274.53  4872.9 1274.02
  4883.6 1274.01  4951.4 1267.41  4977.4 1262.46  5001.7 1260.01  5002.2 1259.51
  5015.8 1260.01  5034.7 1267.49  5077.1 1274.99  5232.0 1273.99  5237.2 1272.63
  5265.7 1272.48  5381.1 1273.96  5590.2 1280.18  5669.9 1284.31  5682.2 1284.45
  5833.2 1288.20  6042.3 1297.20  6109.7 1298.05  6141.5 1298.44  6220.3 1300.18
#Mann=13,-1,0
  4213.3    0.05       0  4360.9    0.12       0  4463.3    0.05       0
  4862.2    0.12       0  4872.9    0.05       0  5001.7    0.05       0
  5015.8    0.05       0  5381.1    0.12       0  5590.2    0.05       0
  5669.9    0.12       0  5682.2    0.05       0  6109.7    0.12       0
  6141.5    0.05       0
Bank Sta=5001.7,5015.8
Exp/Cntr=0.3,0.1

Type RM Length L Ch R = 1,7102,1158,1158,1158
BEGIN DESCRIPTION:
KEENER BRANCH 14.0
END DESCRIPTION:
XS GIS Cut Line= 3
      2787325.62     10151727.23      2787759.19     10150937.15
      2787929.81     10150138.61
#Sta/Elev= 30
  4275.3 1286.28  4402.5 1281.91  4447.0 1280.30  4470.6 1280.28  4476.3 1278.84
  4565.2 1274.37  4689.0 1271.96  4726.5 1271.67  4770.5 1269.12  4798.6 1269.38
  4824.0 1271.43  4911.2 1272.41  4985.7 1259.07  4986.2 1258.57  4999.8 1259.07
  5014.5 1260.38  5036.3 1264.99  5079.9 1267.92  5096.0 1271.10  5201.1 1271.72
  5262.5 1269.16  5303.4 1272.29  5377.6 1275.02  5446.5 1280.09  5456.8 1279.16
  5497.7 1279.61  5599.9 1282.74  5901.6 1294.79  5945.9 1293.97  5993.1 1295.09
#Mann=7,-1,0
  4275.3    0.05       0  4402.5    0.12       0  4447.0    0.05       0
  4689.0    0.12       0  4798.6    0.05       0  4985.7    0.05       0
  4999.8    0.05       0
Bank Sta=4985.7,4999.8
Exp/Cntr=0.3,0.1

Type RM Length L Ch R = 1,5944,336,336,336
BEGIN DESCRIPTION:
KEENER BRANCH 12.0
END DESCRIPTION:
XS GIS Cut Line= 3
      2787905.71     10152553.08      2788695.43     10151419.90
      2788705.68     10151053.16
#Sta/Elev= 30
  3760.0 1292.10  3782.2 1287.38  3796.5 1288.00  3818.0 1287.01  3838.9 1289.08
  3918.4 1285.06  4040.3 1275.81  4169.6 1271.07  4306.6 1268.30  4312.7 1269.04
  4491.6 1267.25  4571.9 1268.53  4744.6 1265.52  4858.1 1266.62  4872.9 1264.48
  4887.7 1258.73  4902.6 1257.45  4908.7 1255.50  4910.2 1253.00  4910.7 1252.50
  4924.6 1253.00  4930.1 1254.29  4944.4 1254.94  5003.2 1253.27  5039.6 1255.19
  5066.6 1264.08  5102.4 1266.93  5132.1 1266.19  5228.0 1267.49  5508.1 1277.31
#Mann=3,-1,0
  3760.0    0.05       0  4910.2    0.03       0  4924.6    0.05       0
Bank Sta=4910.2,4924.6
Exp/Cntr=0.3,0.1

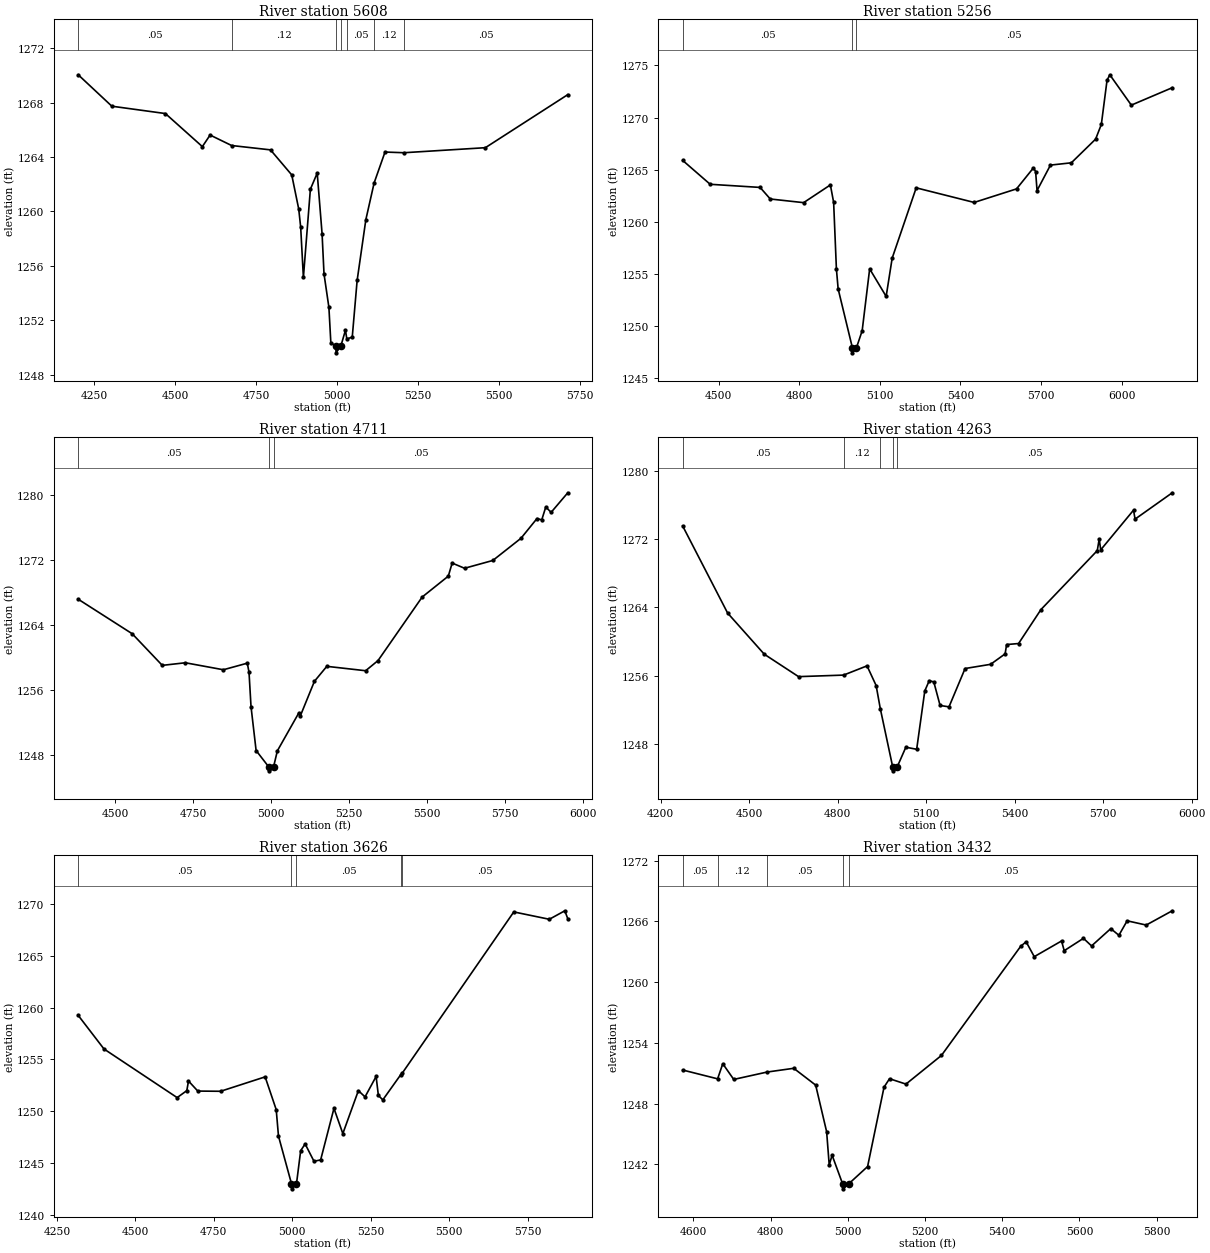
Type RM Length L Ch R = 1,5608,352,352,352
BEGIN DESCRIPTION:
KEENER BRANCH 11.0
END DESCRIPTION:
XS GIS Cut Line= 3
      2788351.67     10152482.42      2788908.97     10151643.86
      2788924.60     10151138.67
#Sta/Elev= 30
  4199.9 1270.05  4303.8 1267.74  4469.2 1267.20  4583.4 1264.77  4607.3 1265.62
  4673.8 1264.85  4793.9 1264.53  4859.5 1262.69  4881.1 1260.18  4887.1 1258.85
  4895.5 1255.15  4917.1 1261.64  4938.2 1262.82  4953.2 1258.37  4959.2 1255.41
  4974.3 1252.95  4980.3 1250.34  4995.8 1250.11  4996.3 1249.61  5011.2 1250.11
  5025.4 1251.27  5029.6 1250.64  5046.4 1250.76  5061.5 1254.93  5088.5 1259.41
  5114.0 1262.10  5147.6 1264.37  5206.0 1264.32  5457.6 1264.69  5712.2 1268.59
#Mann=7,-1,0
  4199.9    0.05       0  4673.8    0.12       0  4995.8    0.07       0
  5011.2    0.12       0  5029.6    0.05       0  5114.0    0.12       0
  5206.0    0.05       0
Bank Sta=4995.8,5011.2
Exp/Cntr=0.3,0.1

Type RM Length L Ch R = 1,5256,545,545,545
BEGIN DESCRIPTION:
KEENER BRANCH 10.0
END DESCRIPTION:
XS GIS Cut Line= 3
      2788711.07     10152664.67      2789105.68     10151877.07
      2789397.54     10150982.19
#Sta/Elev= 30
  4366.4 1265.89  4468.8 1263.60  4654.6 1263.30  4692.5 1262.19  4816.6 1261.84
  4916.2 1263.54  4928.3 1261.87  4938.6 1255.49  4945.1 1253.57  4998.0 1247.94
  4998.5 1247.44  5013.4 1247.94  5034.5 1249.56  5062.4 1255.49  5123.8 1252.85
  5146.2 1256.52  5235.6 1263.26  5451.3 1261.86  5609.1 1263.16  5672.2 1265.18
  5680.1 1264.82  5685.4 1263.00  5735.3 1265.44  5813.0 1265.66  5903.4 1267.93
  5924.7 1269.34  5945.9 1273.57  5956.2 1274.10  6036.3 1271.19  6188.6 1272.86
#Mann=3,-1,0
  4366.4    0.05       0  4998.0    0.03       0  5013.4    0.05       0
Bank Sta=4998,5013.4
Exp/Cntr=0.3,0.1

Type RM Length L Ch R = 1,4711,448,448,448
BEGIN DESCRIPTION:
KEENER BRANCH 9.0
END DESCRIPTION:
XS GIS Cut Line= 3
      2789205.68     10152903.13      2789471.50     10152345.00
      2789882.80     10151487.88
#Sta/Elev= 30
  4381.8 1267.23  4554.9 1262.98  4651.2 1259.09  4725.2 1259.41  4847.0 1258.55
  4923.7 1259.36  4929.2 1258.23  4935.6 1254.01  4951.9 1248.61  4992.1 1246.61
  4992.6 1246.11  5007.9 1246.61  5020.0 1248.57  5087.9 1253.18  5093.5 1252.86
  5138.8 1257.13  5178.5 1258.97  5302.9 1258.43  5342.6 1259.68  5484.1 1267.50
  5567.8 1270.07  5580.2 1271.68  5619.9 1271.04  5710.5 1272.00  5800.7 1274.73
  5852.0 1277.16  5867.3 1277.00  5880.2 1278.58  5897.3 1277.92  5950.7 1280.33
#Mann=3,-1,0
  4381.8    0.05       0  4992.1    0.05       0  5007.9    0.05       0
Bank Sta=4992.1,5007.9
Exp/Cntr=0.3,0.1

Type RM Length L Ch R = 1,4263,637,637,637
BEGIN DESCRIPTION:
KEENER BRANCH 8.0
END DESCRIPTION:
XS GIS Cut Line= 3
      2789455.68     10153203.12      2789956.27     10152385.14
      2790132.70     10151707.23
#Sta/Elev= 30
  4274.7 1273.52  4427.1 1263.34  4551.4 1258.53  4667.5 1255.91  4820.1 1256.09
  4899.6 1257.17  4930.5 1254.87  4944.6 1252.17  4986.4 1245.40  4986.9 1244.90
  5002.4 1245.40  5031.2 1247.66  5067.9 1247.42  5095.4 1254.24  5110.5 1255.44
  5126.0 1255.29  5147.3 1252.54  5177.5 1252.38  5232.0 1256.86  5318.5 1257.35
  5367.7 1258.57  5372.8 1259.66  5413.3 1259.78  5489.2 1263.75  5680.1 1270.64
  5686.6 1271.99  5691.8 1270.73  5803.0 1275.37  5808.2 1274.32  5934.2 1277.40
#Mann=5,-1,0
  4274.7    0.05       0  4820.1    0.12       0  4944.6    0.05       0
  4986.4    0.03       0  5002.4    0.05       0
Bank Sta=4986.4,5002.4
Exp/Cntr=0.3,0.1

Type RM Length L Ch R = 1,3626,194,194,194
BEGIN DESCRIPTION:
KEENER BRANCH 7.0
END DESCRIPTION:
XS GIS Cut Line= 3
      2789763.12     10153248.03      2790205.85     10153070.94
      2790960.86     10152295.11
#Sta/Elev= 30
  4318.1 1259.24  4400.2 1256.00  4633.2 1251.31  4664.0 1251.98  4669.4 1252.91
  4699.0 1251.94  4771.7 1251.92  4913.5 1253.31  4948.8 1250.15  4956.0 1247.60
  4997.4 1243.01  4997.9 1242.51  5013.4 1243.01  5026.7 1246.19  5040.9 1246.84
  5069.1 1245.17  5090.3 1245.30  5132.7 1250.27  5161.0 1247.84  5210.5 1251.98
  5231.7 1251.38  5267.0 1253.35  5274.2 1251.52  5288.3 1251.09  5345.7 1253.53
  5350.5 1253.68  5705.5 1269.22  5818.7 1268.51  5868.1 1269.33  5877.5 1268.56
#Mann=5,-1,0
  4318.1    0.05       0  4997.4    0.03       0  5013.4    0.05       0
  5345.7    0.12       0  5350.5    0.05       0
Bank Sta=4997.4,5013.4
Exp/Cntr=0.3,0.1

Type RM Length L Ch R = 1,3432,692,692,692
BEGIN DESCRIPTION:
KEENER BRANCH 6.0
END DESCRIPTION:
XS GIS Cut Line= 3
      2790205.83     10153289.71      2790737.10     10152810.53
      2791117.32     10152409.47
#Sta/Elev= 30
  4572.3 1251.32  4662.8 1250.45  4676.2 1251.94  4704.6 1250.39  4791.0 1251.12
  4860.0 1251.49  4916.8 1249.83  4945.2 1245.23  4951.9 1241.95  4959.4 1242.91
  4986.5 1240.09  4987.0 1239.59  5002.6 1240.09  5051.3 1241.79  5093.9 1249.63
  5108.1 1250.46  5150.7 1249.93  5242.6 1252.76  5447.8 1263.53  5461.9 1263.98
  5483.0 1262.51  5553.7 1264.06  5560.6 1263.10  5610.4 1264.32  5631.4 1263.57
  5681.2 1265.28  5702.2 1264.62  5723.6 1266.05  5773.0 1265.63  5840.4 1267.04
#Mann=5,-1,0
  4572.3    0.05       0  4662.8    0.12       0  4791.0    0.05       0
  4986.5    0.05       0  5002.6    0.05       0
Bank Sta=4986.5,5002.6
Exp/Cntr=0.3,0.1

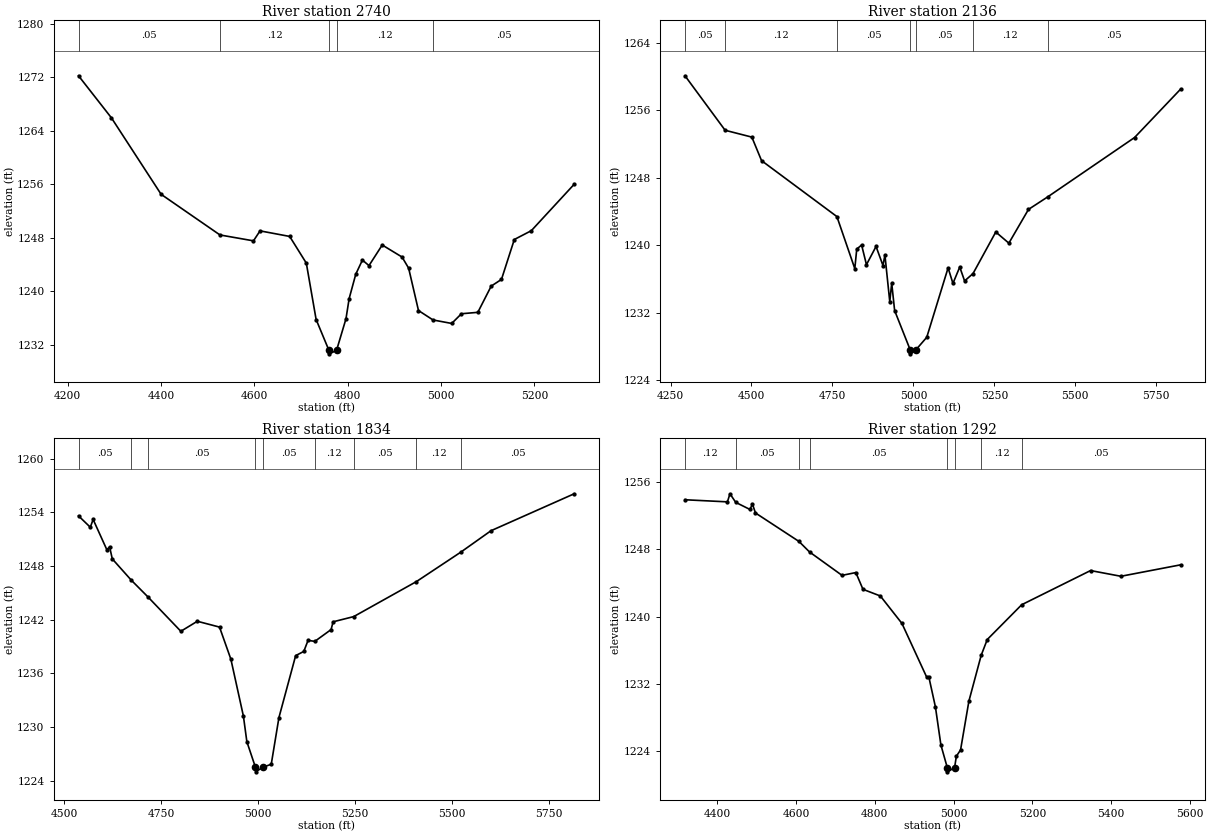
Type RM Length L Ch R = 1,2740,604,604,604
BEGIN DESCRIPTION:
KEENER BRANCH 5.0
END DESCRIPTION:
XS GIS Cut Line= 3
      2790505.68     10153903.12      2791073.75     10153373.00
      2791255.69     10153153.11
#Sta/Elev= 30
  4223.0 1272.22  4293.6 1265.93  4400.1 1254.51  4526.2 1248.44  4598.0 1247.56
  4612.1 1249.05  4675.6 1248.22  4711.3 1244.23  4732.3 1235.81  4759.9 1231.18
  4760.4 1230.68  4776.0 1231.18  4796.3 1235.92  4803.1 1238.94  4817.3 1242.58
  4831.5 1244.69  4845.6 1243.86  4874.0 1246.94  4916.5 1245.14  4930.6 1243.48
  4951.7 1237.15  4982.9 1235.74  5022.9 1235.22  5043.8 1236.67  5078.9 1236.88
  5107.6 1240.80  5129.6 1241.80  5157.1 1247.76  5193.6 1249.08  5285.4 1256.01
#Mann=5,-1,0
  4223.0    0.05       0  4526.2    0.12       0  4759.9    0.05       0
  4776.0    0.12       0  4982.9    0.05       0
Bank Sta=4759.9,4776
Exp/Cntr=0.3,0.1

Type RM Length L Ch R = 1,2136,302,302,302
BEGIN DESCRIPTION:
KEENER BRANCH 4.0
END DESCRIPTION:
XS GIS Cut Line= 3
      2791007.94     10154373.02      2791497.51     10153643.86
      2791591.25     10152998.10
#Sta/Elev= 30
  4294.6 1260.10  4418.6 1253.64  4501.1 1252.83  4531.1 1250.04  4763.8 1243.41
  4819.1 1237.24  4825.1 1239.56  4840.1 1240.04  4855.1 1237.71  4884.7 1239.87
  4906.1 1237.61  4912.1 1238.85  4927.1 1233.32  4933.1 1235.51  4942.1 1232.27
  4989.9 1227.64  4990.4 1227.14  5008.3 1227.64  5041.3 1229.10  5107.2 1237.33
  5122.2 1235.49  5143.2 1237.43  5158.2 1235.78  5184.3 1236.66  5254.5 1241.58
  5294.9 1240.26  5355.5 1244.26  5414.3 1245.73  5683.1 1252.78  5825.4 1258.52
#Mann=7,-1,0
  4294.6    0.05       0  4418.6    0.12       0  4763.8    0.05       0
  4989.9    0.05       0  5008.3    0.05       0  5184.3    0.12       0
  5414.3    0.05       0
Bank Sta=4989.9,5008.3
Exp/Cntr=0.3,0.1

Type RM Length L Ch R = 1,1834,542,542,542
BEGIN DESCRIPTION:
KEENER BRANCH 3.0
END DESCRIPTION:
XS GIS Cut Line= 3
      2791393.38     10154274.04      2791642.45     10154012.54
      2791919.37     10153138.70
#Sta/Elev= 30
  4537.1 1253.60  4567.5 1252.33  4574.8 1253.20  4610.0 1249.83  4617.3 1250.13
  4624.2 1248.79  4673.2 1246.41  4715.9 1244.55  4800.9 1240.70  4843.4 1241.82
  4900.6 1241.17  4929.9 1237.58  4962.2 1231.22  4971.1 1228.36  4993.3 1225.49
  4993.8 1224.99  5011.8 1225.49  5034.0 1225.84  5053.8 1231.06  5096.9 1237.98
  5117.9 1238.45  5128.9 1239.69  5146.2 1239.57  5188.2 1240.89  5193.5 1241.76
  5246.5 1242.34  5408.4 1246.26  5522.1 1249.53  5600.5 1251.94  5814.9 1256.07
#Mann=9,-1,0
  4537.1    0.05       0  4673.2    0.12       0  4715.9    0.05       0
  4993.3    0.05       0  5011.8    0.05       0  5146.2    0.12       0
  5246.5    0.05       0  5408.4    0.12       0  5522.1    0.05       0
Bank Sta=4993.3,5011.8
Exp/Cntr=0.3,0.1

Type RM Length L Ch R = 1,1292,0,0,0
BEGIN DESCRIPTION:
KEENER BRANCH 2.0
END DESCRIPTION:
XS GIS Cut Line= 4
      2791809.99     10154649.09      2792105.68     10154303.11
      2792293.33     10153780.23      2792190.21     10153555.30
#Sta/Elev= 30
  4318.0 1253.90  4425.7 1253.65  4432.2 1254.61  4446.8 1253.59  4482.8 1252.75
  4489.3 1253.38  4496.9 1252.33  4607.3 1248.95  4634.1 1247.70  4716.6 1244.92
  4751.7 1245.25  4769.8 1243.26  4813.9 1242.47  4868.7 1239.21  4931.6 1232.82
  4936.9 1232.87  4953.7 1229.29  4967.6 1224.77  4983.8 1222.08  4984.3 1221.58
  5002.3 1222.08  5006.9 1223.44  5017.5 1224.18  5038.7 1229.99  5069.9 1235.43
  5085.3 1237.30  5172.7 1241.43  5347.5 1245.49  5424.5 1244.81  5576.1 1246.17
#Mann=8,-1,0
  4318.0    0.12       0  4446.8    0.05       0  4607.3    0.12       0
  4634.1    0.05       0  4983.8    0.03       0  5002.3    0.05       0
  5069.9    0.12       0  5172.7    0.05       0
Bank Sta=4983.8,5002.3
Exp/Cntr=0.3,0.1

Chan Stop Cuts=-1