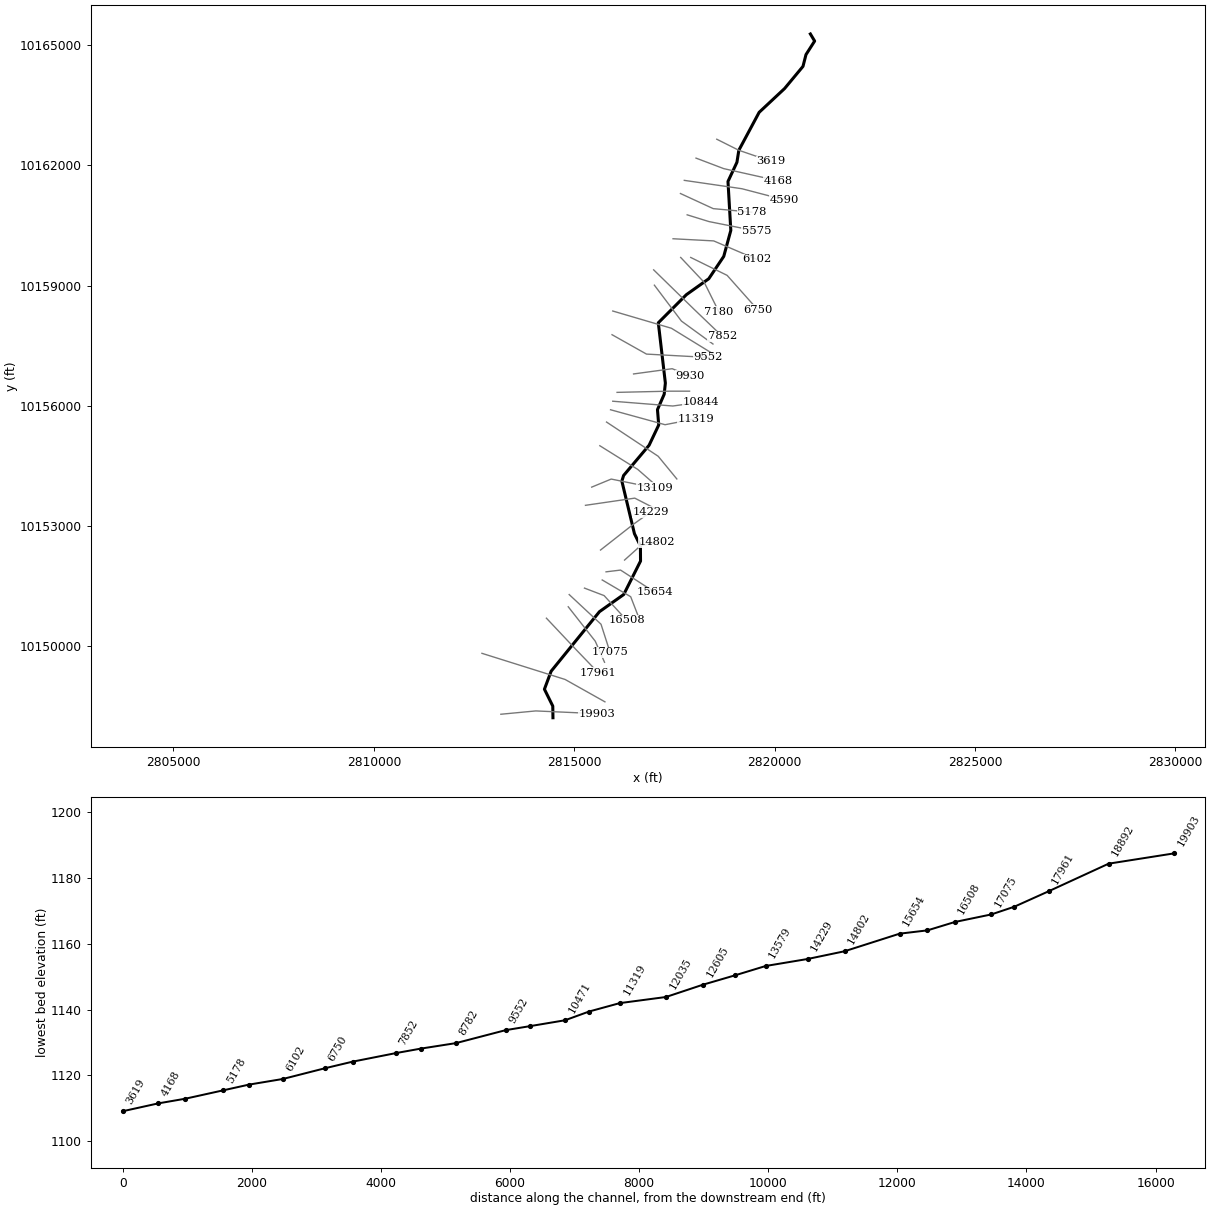
--- LEGION CREEK.prj (project) ---

Proj Title=LEGION CREEK Base Level Engineering
Current Plan=p01
Default Exp/Contr=0.3,0.1
English Units
Geom File=g01
Flow File=f01
Plan File=p01
BEGIN DESCRIPTION:
LEGION CREEK
END DESCRIPTION:

--- LEGION CREEK.p01 (plan) ---

Plan Title=Multiple Run
Short Identifier=Multiple
Geom File=g01
Flow File=f01
Subcritical Flow
K Sum by GR= 0
Std Step Tol= 0.01
Critical Tol= 0.01
Num of Std Step Trials= 20
Max Error Tol= 0.3
Flow Tol Ratio= 0.001
Split Flow NTrial= 30
Split Flow Tol= 0.02
Split Flow Ratio= 0.02
Log Output Level= 0
Friction Slope Method= 1
Unsteady Friction Slope Method= 2
Unsteady Bridges Friction Slope Method= 1
Parabolic Critical Depth
Global Vel Dist=  1 , 1 , 1
Global Log Level= 0
CheckData=True
Encroach Param= -1, 0, 0, 0
BEGIN DESCRIPTION:
Multiple Run
END DESCRIPTION:

--- LEGION CREEK.f01 (steady flow) ---

Flow Title=Multiple
Number of Profiles=7
Profile Names=10-year,25-year,50-year,1pct_min,100-year,1pct_plu,500-year
River Rch & RM= LEGION CREEK,Reach-1,19903
    2982    5508   12443    9202   18570   37474   26471
River Rch & RM= LEGION CREEK,Reach-1,17430
    3718    6966   14824   10884   22035   44610   31066
River Rch & RM= LEGION CREEK,Reach-1,16508
    4359    8230   16886   12379   25025   50588   35014
River Rch & RM= LEGION CREEK,Reach-1,16086
    7052   13492   25230   18021   37067   76242   50828
River Rch & RM= LEGION CREEK,Reach-1,11319
    7843   15022   27576   19469   40429   83956   55202
River Rch & RM= LEGION CREEK,Reach-1,8782
    8868   16993   30591   21327   44739   93852   60788
River Rch & RM= LEGION CREEK,Reach-1,5575
    8454   16193   29181   19969   42726   91416   58141
Boundary for River Rch & Prof#=LEGION CREEK,Reach-1,1
Up Type=0
Dn Type=3
Dn Slope=0.005
Boundary for River Rch & Prof#=LEGION CREEK,Reach-1,2
Up Type=0
Dn Type=3
Dn Slope=0.005
Boundary for River Rch & Prof#=LEGION CREEK,Reach-1,3
Up Type=0
Dn Type=3
Dn Slope=0.005
Boundary for River Rch & Prof#=LEGION CREEK,Reach-1,4
Up Type=0
Dn Type=3
Dn Slope=0.005
Boundary for River Rch & Prof#=LEGION CREEK,Reach-1,5
Up Type=0
Dn Type=3
Dn Slope=0.005
Boundary for River Rch & Prof#=LEGION CREEK,Reach-1,6
Up Type=0
Dn Type=3
Dn Slope=0.005
Boundary for River Rch & Prof#=LEGION CREEK,Reach-1,7
Up Type=0
Dn Type=3
Dn Slope=0.005

--- LEGION CREEK.g01 (geometry) ---

Geom Title=Existing Conditions

River Reach=LEGION CREEK,Reach-1
Reach XY= 30
      2814468.87     10148218.81      2814464.53     10148509.61
      2814256.19     10148930.61      2814423.25     10149379.00
      2815629.00     10150865.00      2816235.00     10151294.00
      2816654.00     10152128.00      2816651.25     10152508.00
      2816502.00     10152811.00      2816188.00     10154123.00
      2816231.50     10154263.00      2816868.00     10155018.00
      2817107.75     10155523.00      2817076.50     10155906.00
      2817244.00     10156290.00      2817273.50     10156569.00
      2817097.50     10158073.00      2817797.25     10158774.00
      2818356.50     10159172.00      2818730.00     10159729.00
      2818906.50     10160378.00      2818835.75     10161599.00
      2819059.00     10162077.00      2819106.50     10162377.00
      2819613.50     10163324.00      2820247.75     10163917.00
      2820707.00     10164470.00      2820782.00     10164764.00
      2820997.75     10165102.00      2820891.75     10165279.00

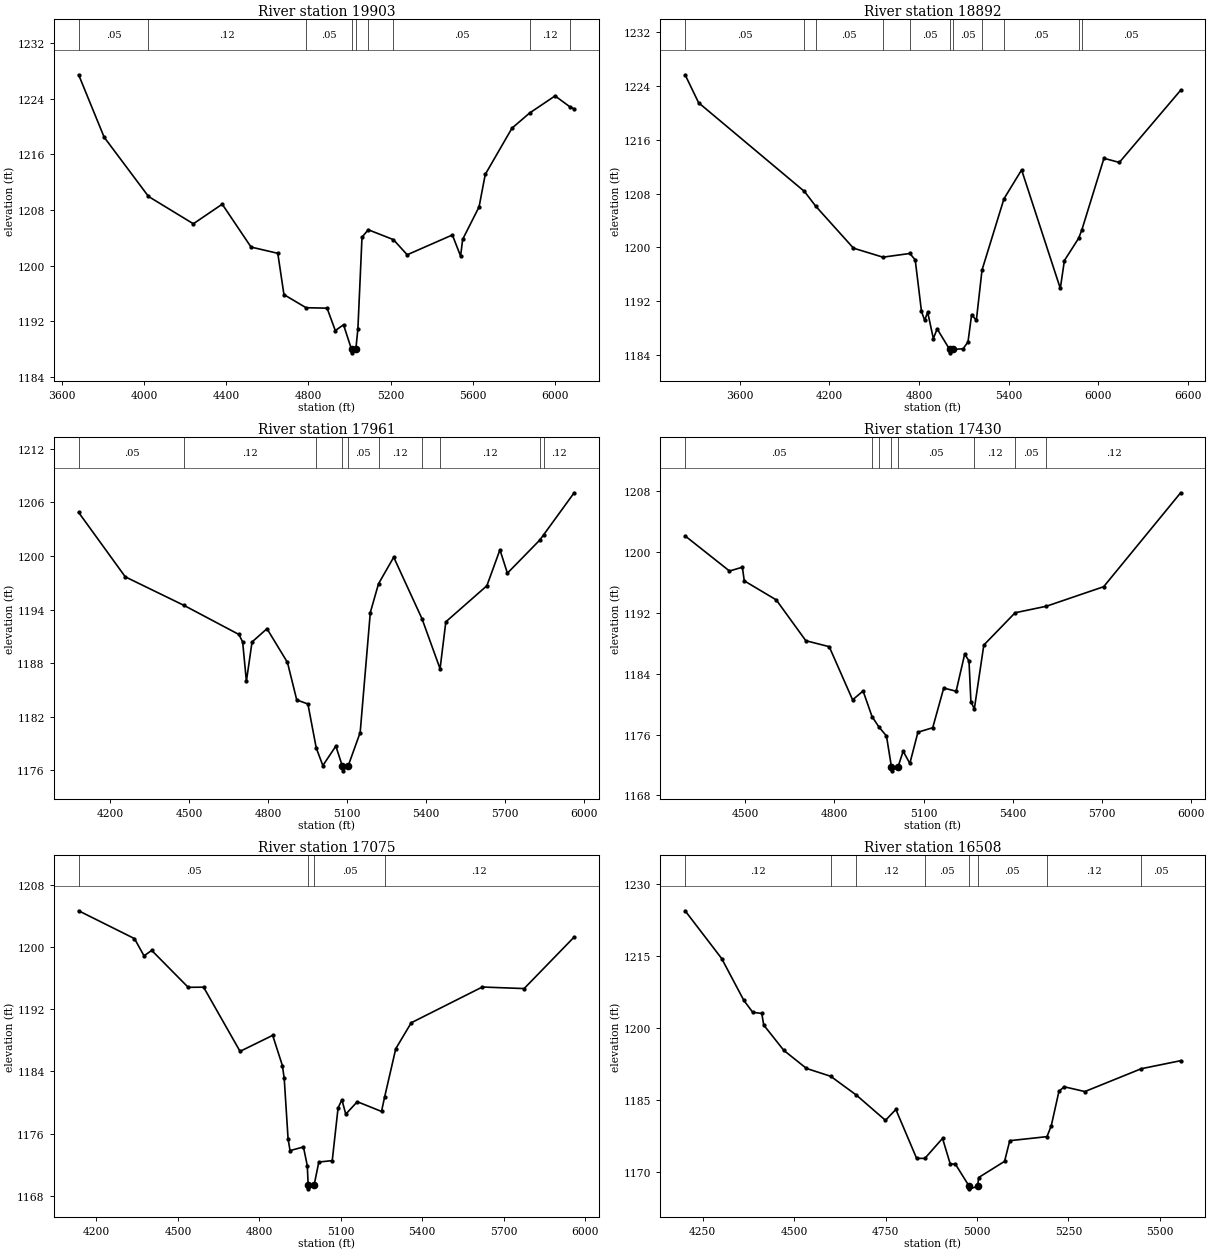
Type RM Length L Ch R = 1,19903,1011,1011,1011
BEGIN DESCRIPTION:
LEGION CREEK 34.0
END DESCRIPTION:
XS GIS Cut Line= 3
      2813169.13     10148306.14      2814040.69     10148388.97
      2815578.58     10148320.54
#Sta/Elev= 30
  3679.9 1227.45  3804.2 1218.47  4020.4 1209.94  4239.0 1206.01  4379.6 1208.83
  4520.2 1202.66  4650.5 1201.76  4680.5 1195.82  4788.4 1193.93  4890.7 1193.87
  4930.8 1190.64  4970.8 1191.48  5009.8 1187.94  5010.3 1187.44  5030.7 1187.94
  5040.9 1190.89  5060.9 1204.08  5091.3 1205.15  5214.0 1203.73  5281.1 1201.55
  5501.3 1204.40  5541.4 1201.36  5551.4 1203.77  5631.4 1208.44  5661.5 1213.11
  5791.6 1219.76  5877.4 1221.94  6001.8 1224.41  6075.4 1222.81  6094.8 1222.55
#Mann=9,-1,0
  3679.9    0.05       0  4020.4    0.12       0  4788.4    0.05       0
  5009.8    0.05       0  5030.7    0.05       0  5091.3    0.12       0
  5214.0    0.05       0  5877.4    0.12       0  6075.4    0.05       0
Bank Sta=5009.8,5030.7
Exp/Cntr=0.3,0.1

Type RM Length L Ch R = 1,18892,931,931,931
BEGIN DESCRIPTION:
Mapping XS a10d8a25
END DESCRIPTION:
XS GIS Cut Line= 3
      2812697.29     10149825.98      2814771.80     10149174.10
      2815765.84     10148615.85
#Sta/Elev= 30
  3235.2 1225.68  3325.4 1221.52  4033.6 1208.32  4108.2 1206.15  4361.3 1199.89
  4558.3 1198.55  4738.7 1199.10  4774.4 1198.14  4816.3 1190.48  4837.3 1189.18
  4857.8 1190.35  4895.5 1186.45  4921.1 1187.88  5004.9 1184.82  5005.4 1184.32
  5026.0 1184.82  5095.1 1184.93  5127.5 1185.96  5151.7 1190.01  5183.2 1189.14
  5221.2 1196.63  5368.1 1207.24  5486.0 1211.53  5744.9 1193.90  5772.3 1198.05
  5866.9 1201.34  5888.1 1202.54  6036.9 1213.26  6139.6 1212.64  6549.8 1223.38
#Mann=11,-1,0
  3235.2    0.05       0  4033.6    0.12       0  4108.2    0.05       0
  4558.3    0.12       0  4738.7    0.05       0  5004.9    0.05       0
  5026.0    0.05       0  5221.2    0.12       0  5368.1    0.05       0
  5866.9    0.12       0  5888.1    0.05       0
Bank Sta=5004.9,5026
Exp/Cntr=0.3,0.1

Type RM Length L Ch R = 1,17961,531,531,531
BEGIN DESCRIPTION:
LEGION CREEK 33.0
END DESCRIPTION:
XS GIS Cut Line= 3
      2814305.69     10150703.11      2815065.23     10149897.50
      2815601.57     10149340.72
#Sta/Elev= 30
  4081.3 1204.88  4258.3 1197.66  4481.8 1194.45  4689.6 1191.20  4703.7 1190.36
  4717.9 1185.96  4739.3 1190.36  4796.0 1191.85  4873.7 1188.07  4908.9 1183.87
  4951.3 1183.41  4982.9 1178.49  5008.0 1176.51  5057.3 1178.69  5082.4 1176.42
  5082.9 1175.92  5103.5 1176.42  5149.6 1180.21  5188.1 1193.66  5219.2 1196.88
  5276.9 1199.86  5384.3 1192.96  5452.8 1187.36  5474.7 1192.62  5630.4 1196.66
  5680.0 1200.69  5708.3 1198.07  5831.2 1201.78  5846.0 1202.38  5961.6 1207.08
#Mann=10,-1,0
  4081.3    0.05       0  4481.8    0.12       0  4982.9    0.05       0
  5082.4    0.05       0  5103.5    0.05       0  5219.2    0.12       0
  5384.3    0.05       0  5452.8    0.12       0  5831.2    0.05       0
  5846.0    0.12       0
Bank Sta=5082.4,5103.5
Exp/Cntr=0.3,0.1

Type RM Length L Ch R = 1,17430,355,355,355
BEGIN DESCRIPTION:
LEGION CREEK 32.0
END DESCRIPTION:
XS GIS Cut Line= 3
      2814850.23     10150987.55      2815524.84     10150127.86
      2815755.70     10149603.07
#Sta/Elev= 30
  4298.4 1202.07  4447.6 1197.46  4490.9 1197.96  4497.3 1196.17  4604.8 1193.67
  4704.3 1188.31  4782.9 1187.53  4861.5 1180.55  4896.8 1181.71  4926.8 1178.36
  4950.3 1176.97  4975.4 1175.81  4992.2 1171.73  4992.7 1171.23  5014.1 1171.73
  5031.5 1173.81  5054.0 1172.20  5081.2 1176.30  5130.9 1176.89  5168.0 1182.10
  5209.6 1181.68  5238.5 1186.57  5252.9 1185.64  5259.3 1180.32  5270.8 1179.35
  5302.7 1187.74  5407.9 1191.98  5513.3 1192.84  5705.7 1195.40  5964.5 1207.73
#Mann=8,-1,0
  4298.4    0.05       0  4926.8    0.12       0  4950.3    0.05       0
  4992.2    0.05       0  5014.1    0.05       0  5270.8    0.12       0
  5407.9    0.05       0  5513.3    0.12       0
Bank Sta=4992.2,5014.1
Exp/Cntr=0.3,0.1

Type RM Length L Ch R = 1,17075,567,567,567
BEGIN DESCRIPTION:
LEGION CREEK 31.0
END DESCRIPTION:
XS GIS Cut Line= 3
      2814874.09     10151292.04      2815668.12     10150551.75
      2815894.86     10149847.65
#Sta/Elev= 30
  4134.2 1204.68  4339.9 1201.10  4375.1 1198.88  4403.4 1199.58  4537.8 1194.83
  4594.5 1194.85  4728.8 1186.59  4849.0 1188.65  4884.7 1184.77  4891.5 1183.11
  4905.7 1175.33  4913.0 1173.82  4962.3 1174.29  4976.5 1171.88  4979.7 1169.40
  4980.2 1168.90  5001.7 1169.40  5019.0 1172.35  5068.4 1172.53  5089.9 1179.32
  5104.0 1180.36  5118.2 1178.51  5160.7 1180.11  5249.9 1178.86  5261.4 1180.72
  5302.4 1186.93  5359.4 1190.27  5621.2 1194.87  5775.2 1194.67  5959.5 1201.30
#Mann=4,-1,0
  4134.2    0.05       0  4979.7    0.05       0  5001.7    0.05       0
  5261.4    0.12       0
Bank Sta=4979.7,5001.7
Exp/Cntr=0.3,0.1

Type RM Length L Ch R = 1,16508,422,422,422
BEGIN DESCRIPTION:
LEGION CREEK 30.0
END DESCRIPTION:
XS GIS Cut Line= 3
      2815255.66     10151453.12      2815745.65     10151266.09
      2816305.71     10150653.09
#Sta/Elev= 30
  4202.1 1224.44  4302.0 1214.51  4362.7 1205.79  4386.9 1203.33  4411.7 1203.07
  4417.0 1200.67  4471.8 1195.41  4533.9 1191.64  4600.0 1190.01  4669.9 1186.12
  4749.9 1180.84  4778.3 1183.11  4835.0 1172.94  4857.5 1172.92  4905.9 1177.09
  4926.9 1171.78  4941.1 1171.73  4979.1 1167.09  4979.6 1166.59  5001.8 1167.09
  5004.6 1168.94  5075.5 1172.31  5089.7 1176.61  5191.5 1177.45  5203.2 1179.72
  5224.1 1186.86  5238.3 1187.83  5295.1 1186.83  5449.3 1191.58  5556.9 1193.25
#Mann=8,-1,0
  4202.1    0.12       0  4600.0    0.05       0  4669.9    0.12       0
  4857.5    0.05       0  4979.1    0.05       0  5001.8    0.05       0
  5191.5    0.12       0  5449.3    0.05       0
Bank Sta=4979.1,5001.8
Exp/Cntr=0.3,0.1

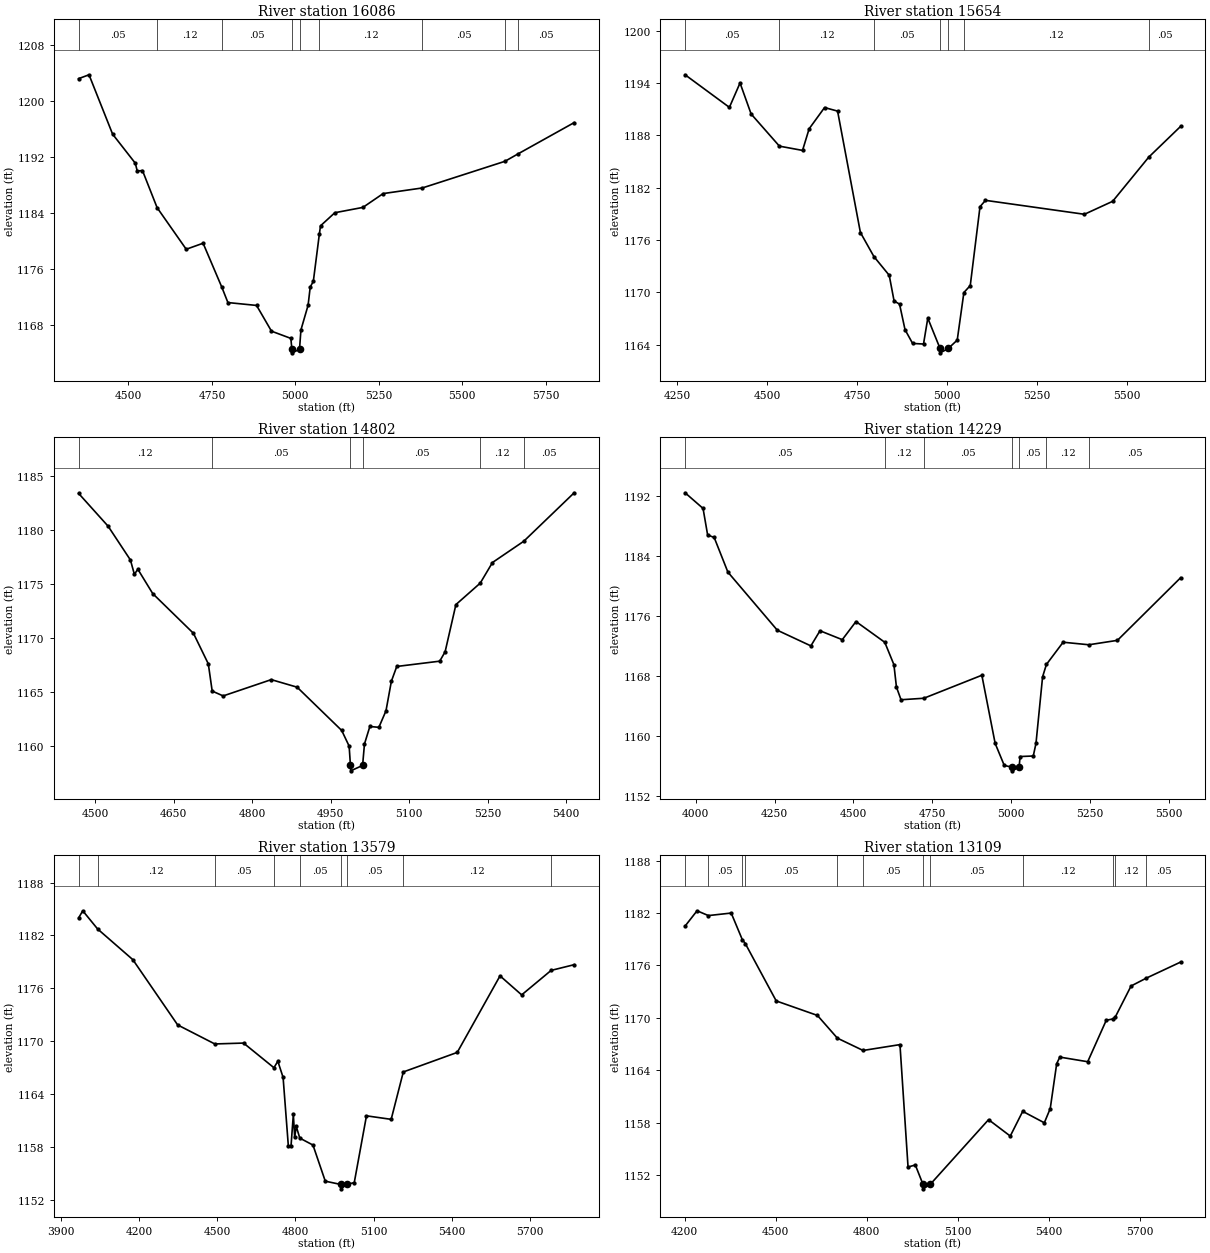
Type RM Length L Ch R = 1,16086,432,432,432
BEGIN DESCRIPTION:
LEGION CREEK 29.0
END DESCRIPTION:
XS GIS Cut Line= 3
      2815697.95     10151656.24      2816408.42     10151238.31
      2816647.21     10150623.43
#Sta/Elev= 30
  4351.0 1203.16  4382.1 1203.71  4452.8 1195.24  4520.7 1191.10  4526.5 1189.99
  4542.2 1190.05  4586.0 1184.76  4673.2 1178.83  4723.7 1179.69  4779.8 1173.42
  4798.0 1171.23  4883.8 1170.82  4928.5 1167.15  4986.5 1166.12  4989.6 1164.56
  4990.1 1164.06  5012.4 1164.56  5016.7 1167.33  5038.1 1170.84  5044.5 1173.45
  5053.8 1174.25  5071.9 1181.01  5075.3 1182.17  5118.2 1184.04  5202.3 1184.80
  5262.9 1186.77  5380.1 1187.57  5627.5 1191.37  5667.9 1192.46  5834.9 1196.89
#Mann=9,-1,0
  4351.0    0.05       0  4586.0    0.12       0  4779.8    0.05       0
  4989.6    0.05       0  5012.4    0.05       0  5071.9    0.12       0
  5380.1    0.05       0  5627.5    0.12       0  5667.9    0.05       0
Bank Sta=4989.6,5012.4
Exp/Cntr=0.3,0.1

Type RM Length L Ch R = 1,15654,852,852,852
BEGIN DESCRIPTION:
LEGION CREEK 28.0
END DESCRIPTION:
XS GIS Cut Line= 3
      2815793.52     10151859.21      2816155.68     10151903.11
      2817005.65     10151353.13
#Sta/Elev= 30
  4272.2 1194.96  4395.3 1191.22  4424.9 1194.02  4455.7 1190.46  4534.3 1186.77
  4598.6 1186.28  4616.9 1188.76  4659.8 1191.20  4696.0 1190.79  4759.4 1176.86
  4796.9 1174.10  4839.5 1171.95  4853.0 1169.00  4868.2 1168.64  4883.4 1165.71
  4904.5 1164.13  4934.8 1164.06  4946.7 1167.03  4980.8 1163.55  4981.3 1163.05
  5003.6 1163.55  5028.5 1164.51  5047.0 1169.97  5064.7 1170.77  5091.8 1179.82
  5107.0 1180.55  5382.0 1178.95  5460.5 1180.44  5560.8 1185.51  5649.4 1189.04
#Mann=7,-1,0
  4272.2    0.05       0  4534.3    0.12       0  4796.9    0.05       0
  4980.8    0.05       0  5003.6    0.05       0  5047.0    0.12       0
  5560.8    0.05       0
Bank Sta=4980.8,5003.6
Exp/Cntr=0.3,0.1

Type RM Length L Ch R = 1,14802,573,573,573
BEGIN DESCRIPTION:
LEGION CREEK 27.0
END DESCRIPTION:
XS GIS Cut Line= 3
      2816255.71     10152153.13      2816651.25     10152508.00
      2817055.72     10152603.12
#Sta/Elev= 30
  4468.6 1183.41  4525.0 1180.37  4567.6 1177.24  4575.1 1175.92  4581.8 1176.38
  4610.2 1174.13  4688.0 1170.45  4716.4 1167.62  4723.8 1165.10  4744.8 1164.65
  4836.7 1166.16  4886.1 1165.46  4971.3 1161.45  4985.5 1160.00  4988.0 1158.21
  4988.5 1157.71  5011.2 1158.21  5014.8 1160.20  5025.1 1161.82  5042.3 1161.74
  5055.9 1163.27  5066.2 1166.01  5076.5 1167.38  5158.6 1167.87  5168.9 1168.74
  5189.5 1173.11  5236.0 1175.10  5259.4 1177.01  5319.2 1178.98  5415.5 1183.47
#Mann=6,-1,0
  4468.6    0.12       0  4723.8    0.05       0  4988.0    0.05       0
  5011.2    0.05       0  5236.0    0.12       0  5319.2    0.05       0
Bank Sta=4988,5011.2
Exp/Cntr=0.3,0.1

Type RM Length L Ch R = 1,14229,650,650,650
BEGIN DESCRIPTION:
LEGION CREEK 26.0
END DESCRIPTION:
XS GIS Cut Line= 3
      2815655.71     10152403.13      2816469.00     10153041.00
      2816905.72     10153353.14
#Sta/Elev= 30
  3966.4 1192.48  4023.3 1190.39  4037.8 1186.85  4058.6 1186.51  4102.0 1181.89
  4258.7 1174.13  4365.0 1172.04  4393.9 1174.06  4464.5 1172.87  4507.9 1175.29
  4599.2 1172.52  4628.1 1169.54  4636.2 1166.54  4650.7 1164.85  4723.0 1165.05
  4906.8 1168.12  4949.0 1159.02  4977.9 1156.08  5001.7 1155.86  5002.2 1155.36
  5024.9 1155.86  5028.0 1157.27  5069.8 1157.34  5078.4 1159.03  5099.3 1167.91
  5111.4 1169.56  5164.4 1172.53  5245.9 1172.19  5336.5 1172.78  5536.8 1181.14
#Mann=7,-1,0
  3966.4    0.05       0  4599.2    0.12       0  4723.0    0.05       0
  5001.7    0.03       0  5024.9    0.05       0  5111.4    0.12       0
  5245.9    0.05       0
Bank Sta=5001.7,5024.9
Exp/Cntr=0.3,0.1

Type RM Length L Ch R = 1,13579,470,470,470
BEGIN DESCRIPTION:
LEGION CREEK 25.0
END DESCRIPTION:
XS GIS Cut Line= 3
      2815280.08     10153518.91      2816509.91     10153698.01
      2817094.96     10153399.52
#Sta/Elev= 30
  3969.2 1183.99  3985.0 1184.80  4042.1 1182.73  4177.0 1179.25  4348.8 1171.84
  4491.2 1169.68  4601.4 1169.78  4717.9 1166.98  4732.8 1167.72  4753.0 1165.88
  4773.2 1158.06  4783.3 1158.06  4792.3 1161.68  4797.4 1159.08  4803.5 1160.31
  4817.0 1158.99  4867.5 1158.20  4914.7 1154.10  4973.8 1153.73  4974.3 1153.23
  4997.1 1153.73  5025.8 1153.94  5072.6 1161.52  5167.3 1161.12  5213.8 1166.50
  5420.6 1168.72  5584.6 1177.41  5667.5 1175.25  5780.4 1178.03  5868.8 1178.68
#Mann=9,-1,0
  3969.2    0.05       0  4042.1    0.12       0  4491.2    0.05       0
  4717.9    0.12       0  4817.0    0.05       0  4973.8    0.03       0
  4997.1    0.05       0  5213.8    0.12       0  5780.4    0.05       0
Bank Sta=4973.8,4997.1
Exp/Cntr=0.3,0.1

Type RM Length L Ch R = 1,13109,504,504,504
BEGIN DESCRIPTION:
LEGION CREEK 24.0
END DESCRIPTION:
XS GIS Cut Line= 3
      2815435.33     10153972.66      2815922.86     10154173.97
      2817005.70     10153953.11
#Sta/Elev= 30
  4201.3 1180.50  4240.7 1182.25  4278.0 1181.70  4353.2 1181.99  4389.6 1178.96
  4399.6 1178.50  4501.5 1171.93  4637.3 1170.27  4703.0 1167.67  4787.7 1166.26
  4909.2 1166.93  4935.8 1152.92  4959.8 1153.15  4985.2 1150.92  4985.7 1150.42
  5008.7 1150.92  5201.1 1158.34  5272.6 1156.46  5313.6 1159.29  5384.8 1157.98
  5404.3 1159.61  5425.6 1164.76  5435.9 1165.50  5527.7 1164.97  5588.9 1169.72
  5611.4 1169.87  5618.6 1170.09  5670.6 1173.64  5720.2 1174.53  5833.9 1176.38
#Mann=12,-1,0
  4201.3    0.12       0  4278.0    0.05       0  4389.6    0.12       0
  4399.6    0.05       0  4703.0    0.12       0  4787.7    0.05       0
  4985.2    0.03       0  5008.7    0.05       0  5313.6    0.12       0
  5611.4    0.05       0  5618.6    0.12       0  5720.2    0.05       0
Bank Sta=4985.2,5008.7
Exp/Cntr=0.3,0.1

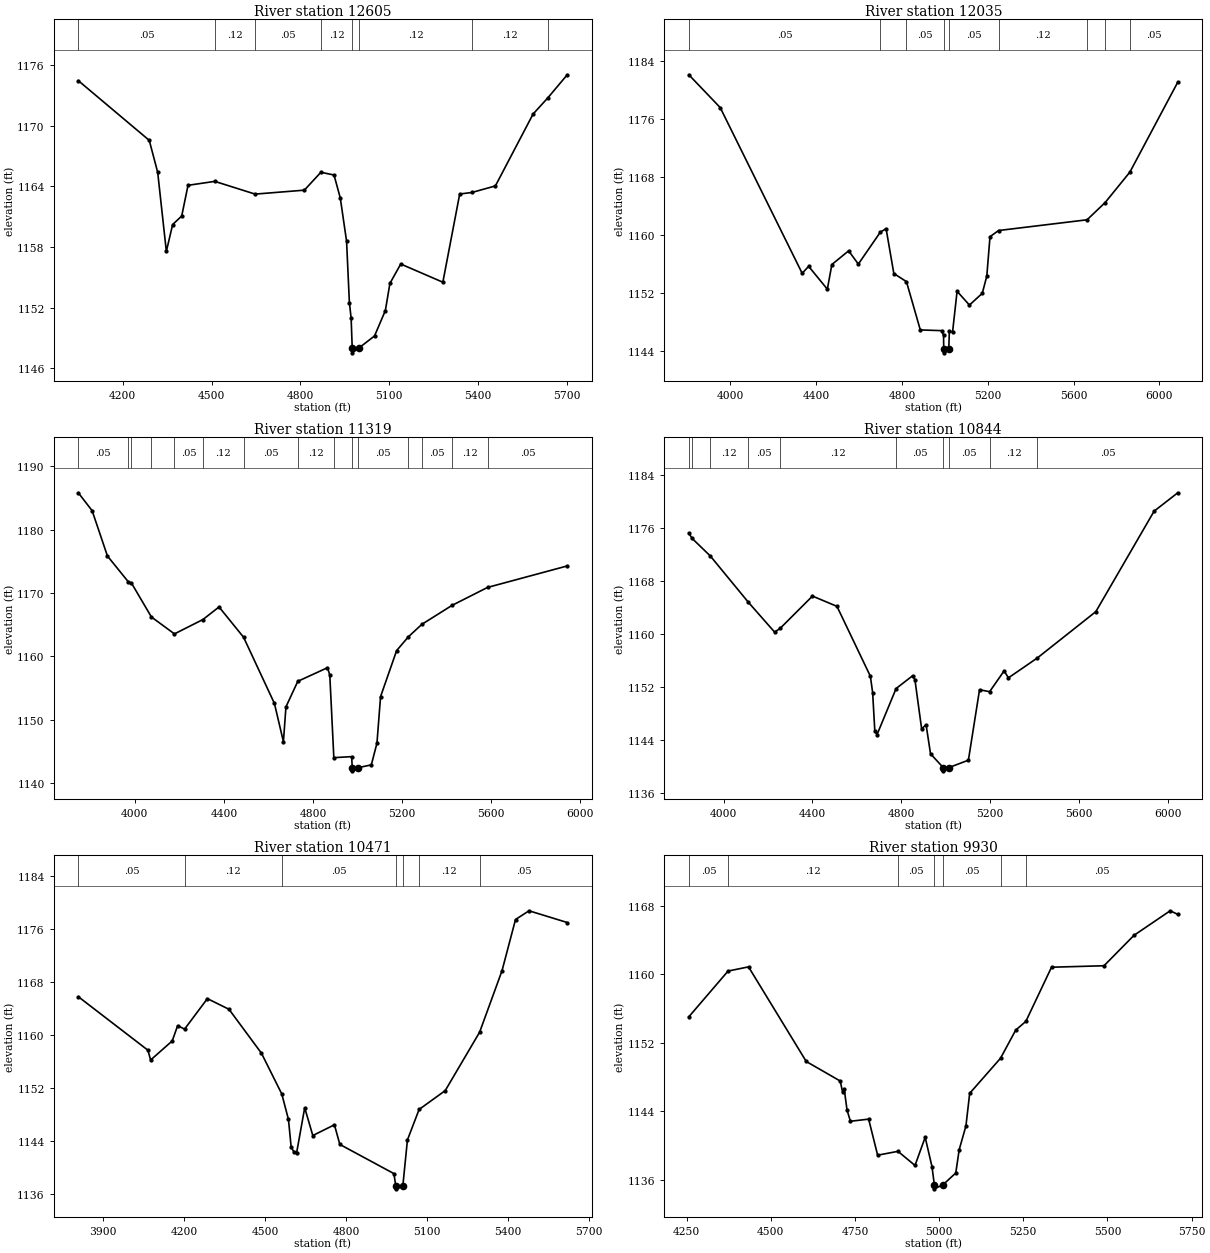
Type RM Length L Ch R = 1,12605,570,570,570
BEGIN DESCRIPTION:
LEGION CREEK 23.0
END DESCRIPTION:
XS GIS Cut Line= 3
      2815638.26     10155005.48      2816586.26     10154413.42
      2816987.55     10154062.17
#Sta/Elev= 30
  4049.7 1174.47  4289.3 1168.56  4317.8 1165.39  4347.0 1157.57  4368.3 1160.23
  4398.9 1161.07  4420.2 1164.11  4510.5 1164.50  4646.8 1163.24  4812.9 1163.63
  4868.9 1165.40  4913.2 1165.13  4934.4 1162.85  4955.6 1158.57  4965.1 1152.49
  4971.0 1150.97  4974.6 1148.03  4975.1 1147.53  4998.1 1148.03  5050.0 1149.20
  5086.6 1151.72  5101.9 1154.40  5138.5 1156.32  5280.7 1154.52  5337.6 1163.25
  5378.5 1163.40  5458.1 1164.05  5585.3 1171.16  5635.6 1172.78  5700.7 1175.05
#Mann=8,-1,0
  4049.7    0.05       0  4510.5    0.12       0  4646.8    0.05       0
  4868.9    0.12       0  4974.6    0.03       0  4998.1    0.12       0
  5378.5    0.12       0  5635.6    0.05       0
Bank Sta=4974.6,4998.1
Exp/Cntr=0.3,0.1

Type RM Length L Ch R = 1,12035,716,716,716
BEGIN DESCRIPTION:
LEGION CREEK 22.0
END DESCRIPTION:
XS GIS Cut Line= 3
      2815805.43     10155596.52      2817094.54     10154742.76
      2817559.65     10154176.86
#Sta/Elev= 30
  3806.7 1182.16  3952.8 1177.64  4334.9 1154.78  4365.0 1155.74  4452.2 1152.59
  4473.3 1155.99  4551.5 1157.88  4596.6 1156.05  4699.1 1160.45  4726.0 1160.94
  4762.1 1154.75  4820.9 1153.63  4885.5 1146.97  4984.7 1146.87  4993.8 1146.22
  4994.7 1144.31  4995.2 1143.81  5018.2 1144.31  5020.8 1146.81  5035.9 1146.70
  5056.9 1152.30  5114.4 1150.40  5174.3 1152.02  5195.3 1154.38  5210.3 1159.83
  5250.2 1160.68  5662.7 1162.16  5746.7 1164.53  5862.3 1168.74  6085.4 1181.14
#Mann=9,-1,0
  3806.7    0.05       0  4699.1    0.12       0  4820.9    0.05       0
  4994.7    0.05       0  5018.2    0.05       0  5250.2    0.12       0
  5662.7    0.05       0  5746.7    0.12       0  5862.3    0.05       0
Bank Sta=4994.7,5018.2
Exp/Cntr=0.3,0.1

Type RM Length L Ch R = 1,11319,475,475,475
BEGIN DESCRIPTION:
LEGION CREEK 21.0
END DESCRIPTION:
XS GIS Cut Line= 3
      2815905.73     10155903.10      2817265.98     10155529.87
      2818038.28     10155680.10
#Sta/Elev= 30
  3745.8 1185.81  3808.0 1182.98  3876.7 1175.84  3970.7 1171.76  3984.4 1171.59
  4074.3 1166.22  4177.9 1163.55  4305.6 1165.81  4378.3 1167.80  4488.6 1163.02
  4627.2 1152.58  4667.6 1146.55  4679.0 1152.04  4732.2 1156.07  4865.7 1158.22
  4876.0 1157.07  4894.2 1144.03  4974.3 1144.19  4976.9 1142.45  4977.4 1141.95
  5003.3 1142.45  5062.7 1142.89  5088.0 1146.33  5104.2 1153.66  5176.4 1160.92
  5229.7 1163.11  5289.8 1165.06  5424.9 1168.04  5584.9 1170.88  5943.1 1174.27
#Mann=15,-1,0
  3745.8    0.05       0  3970.7    0.12       0  3984.4    0.05       0
  4074.3    0.12       0  4177.9    0.05       0  4305.6    0.12       0
  4488.6    0.05       0  4732.2    0.12       0  4894.2    0.05       0
  4976.9    0.05       0  5003.3    0.05       0  5229.7    0.12       0
  5289.8    0.05       0  5424.9    0.12       0  5584.9    0.05       0
Bank Sta=4976.9,5003.3
Exp/Cntr=0.3,0.1

Type RM Length L Ch R = 1,10844,373,373,373
BEGIN DESCRIPTION:
LEGION CREEK 20.0
END DESCRIPTION:
XS GIS Cut Line= 3
      2815960.64     10156115.93      2817459.17     10155996.52
      2818151.24     10156091.98
#Sta/Elev= 30
  3843.6 1175.30  3857.7 1174.52  3940.4 1171.84  4112.1 1164.84  4229.9 1160.35
  4254.7 1160.91  4400.4 1165.79  4510.7 1164.24  4661.2 1153.68  4671.3 1151.23
  4681.3 1145.36  4691.3 1144.88  4777.0 1151.83  4851.8 1153.77  4861.9 1153.14
  4892.0 1145.74  4912.0 1146.37  4932.1 1141.97  4989.1 1139.90  4989.6 1139.40
  5015.5 1139.90  5102.6 1141.01  5152.8 1151.65  5198.1 1151.35  5263.1 1154.48
  5283.2 1153.45  5412.9 1156.44  5676.5 1163.44  5938.9 1178.61  6045.5 1181.39
#Mann=10,-1,0
  3843.6    0.12       0  3857.7    0.05       0  3940.4    0.12       0
  4112.1    0.05       0  4254.7    0.12       0  4777.0    0.05       0
  4989.1    0.05       0  5015.5    0.05       0  5198.1    0.12       0
  5412.9    0.05       0
Bank Sta=4989.1,5015.5
Exp/Cntr=0.3,0.1

Type RM Length L Ch R = 1,10471,541,541,541
BEGIN DESCRIPTION:
LEGION CREEK 19.0
END DESCRIPTION:
XS GIS Cut Line= 3
      2816068.14     10156336.82      2817369.61     10156366.60
      2817877.10     10156366.67
#Sta/Elev= 30
  3809.2 1165.72  4066.8 1157.65  4076.8 1156.17  4156.8 1159.05  4176.8 1161.35
  4202.5 1160.83  4286.9 1165.43  4366.9 1163.82  4486.9 1157.20  4562.2 1151.05
  4586.9 1147.20  4596.9 1143.04  4607.0 1142.31  4617.0 1142.15  4647.0 1148.97
  4677.0 1144.78  4757.0 1146.40  4777.0 1143.44  4977.0 1139.04  4983.9 1137.24
  4984.4 1136.74  5010.3 1137.24  5027.1 1144.11  5070.3 1148.71  5167.1 1151.56
  5294.3 1160.37  5377.1 1169.63  5427.1 1177.36  5477.1 1178.68  5618.5 1176.91
#Mann=7,-1,0
  3809.2    0.05       0  4202.5    0.12       0  4562.2    0.05       0
  4983.9    0.05       0  5010.3    0.05       0  5070.3    0.12       0
  5294.3    0.05       0
Bank Sta=4983.9,5010.3
Exp/Cntr=0.3,0.1

Type RM Length L Ch R = 1,9930,378,378,378
BEGIN DESCRIPTION:
LEGION CREEK 18.0
END DESCRIPTION:
XS GIS Cut Line= 3
      2816480.02     10156796.52      2817443.69     10156927.24
      2817889.05     10156748.75
#Sta/Elev= 30
  4256.5 1155.05  4373.0 1160.39  4433.8 1160.88  4605.3 1149.83  4706.2 1147.55
  4713.0 1146.29  4718.1 1146.60  4726.4 1144.16  4736.5 1142.85  4790.6 1143.10
  4817.3 1138.89  4877.7 1139.34  4928.3 1137.69  4958.5 1140.98  4978.7 1137.56
  4985.7 1135.46  4986.2 1134.96  5012.1 1135.46  5049.4 1136.81  5059.5 1139.52
  5079.6 1142.31  5090.7 1146.11  5182.3 1150.21  5227.5 1153.50  5257.5 1154.51
  5333.8 1160.84  5489.7 1161.01  5578.7 1164.56  5686.3 1167.43  5708.8 1167.01
#Mann=7,-1,0
  4256.5    0.05       0  4373.0    0.12       0  4877.7    0.05       0
  4985.7    0.03       0  5012.1    0.05       0  5182.3    0.12       0
  5257.5    0.05       0
Bank Sta=4985.7,5012.1
Exp/Cntr=0.3,0.1

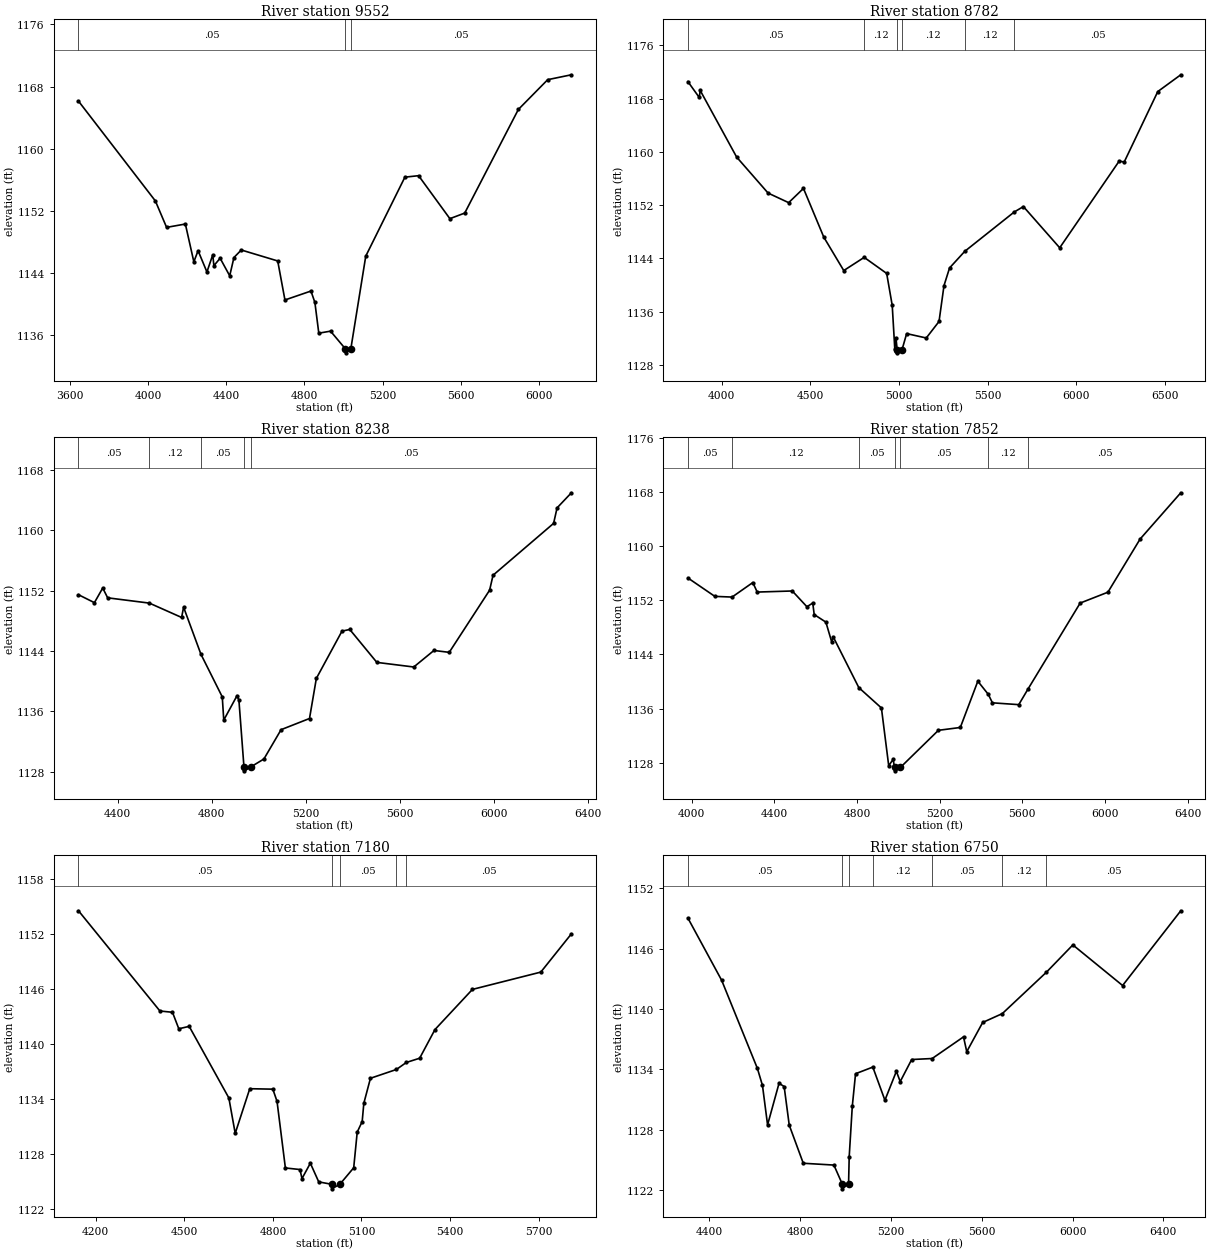
Type RM Length L Ch R = 1,9552,770,770,770
BEGIN DESCRIPTION:
LEGION CREEK 17.0
END DESCRIPTION:
XS GIS Cut Line= 3
      2815942.72     10157775.64      2816802.45     10157292.04
      2818336.77     10157208.46
#Sta/Elev= 30
  3643.3 1166.12  4036.8 1153.28  4094.2 1149.88  4190.3 1150.31  4233.7 1145.45
  4255.4 1146.88  4300.7 1144.14  4330.6 1146.36  4336.3 1144.95  4368.2 1145.91
  4417.3 1143.65  4438.9 1146.00  4476.5 1146.97  4663.0 1145.56  4700.0 1140.54
  4833.2 1141.69  4853.3 1140.22  4873.3 1136.27  4933.4 1136.53  5009.9 1134.24
  5010.4 1133.74  5037.2 1134.24  5113.7 1146.18  5314.0 1156.34  5384.1 1156.53
  5544.3 1151.00  5620.3 1151.72  5894.8 1165.05  6045.0 1168.88  6166.3 1169.51
#Mann=3,-1,0
  3643.3    0.05       0  5009.9    0.03       0  5037.2    0.05       0
Bank Sta=5009.9,5037.2
Exp/Cntr=0.3,0.1

Type RM Length L Ch R = 1,8782,544,544,544
BEGIN DESCRIPTION:
LEGION CREEK 16.0
END DESCRIPTION:
XS GIS Cut Line= 3
      2815960.64     10158366.68      2817423.34     10157936.82
      2818491.34     10157280.51
#Sta/Elev= 30
  3810.1 1170.55  3874.3 1168.16  3879.5 1169.22  4084.9 1159.21  4262.2 1153.80
  4378.2 1152.36  4461.6 1154.50  4576.2 1147.18  4688.7 1142.16  4803.9 1144.14
  4930.6 1141.73  4961.9 1136.93  4976.5 1130.32  4982.7 1132.08  4989.7 1130.30
  4990.2 1129.80  5017.5 1130.30  5043.2 1132.69  5153.7 1132.03  5225.7 1134.51
  5253.7 1139.90  5285.0 1142.55  5370.8 1145.05  5650.2 1150.97  5701.3 1151.77
  5905.9 1145.58  6241.2 1158.61  6269.3 1158.46  6458.7 1169.05  6588.2 1171.57
#Mann=6,-1,0
  3810.1    0.05       0  4803.9    0.12       0  4989.7    0.07       0
  5017.5    0.12       0  5370.8    0.12       0  5650.2    0.05       0
Bank Sta=4989.7,5017.5
Exp/Cntr=0.3,0.1

Type RM Length L Ch R = 1,8238,386,386,386
BEGIN DESCRIPTION:
LEGION CREEK 15.0
END DESCRIPTION:
XS GIS Cut Line= 3
      2816999.47     10159011.44      2817674.09     10158115.92
      2818461.40     10157543.33
#Sta/Elev= 30
  4234.1 1151.45  4301.7 1150.40  4337.1 1152.34  4358.0 1151.04  4535.3 1150.34
  4672.3 1148.44  4680.7 1149.80  4754.4 1143.57  4845.1 1137.92  4851.4 1134.85
  4908.1 1138.10  4915.9 1137.46  4937.3 1128.63  4937.8 1128.13  4965.3 1128.63
  5022.1 1129.70  5095.0 1133.58  5215.8 1135.06  5244.9 1140.37  5353.9 1146.63
  5386.9 1146.85  5502.0 1142.49  5658.9 1141.88  5744.7 1144.07  5809.6 1143.82
  5981.2 1152.05  5995.8 1154.03  6253.2 1160.90  6267.9 1162.95  6328.8 1164.95
#Mann=5,-1,0
  4234.1    0.05       0  4535.3    0.12       0  4754.4    0.05       0
  4937.3    0.03       0  4965.3    0.05       0
Bank Sta=4937.3,4965.3
Exp/Cntr=0.3,0.1

Type RM Length L Ch R = 1,7852,672,672,672
BEGIN DESCRIPTION:
LEGION CREEK 14.0
END DESCRIPTION:
XS GIS Cut Line= 3
      2816981.54     10159393.55      2817978.57     10158420.40
      2818694.98     10157733.84
#Sta/Elev= 30
  3981.9 1155.33  4112.5 1152.60  4195.9 1152.50  4296.2 1154.65  4317.5 1153.24
  4487.3 1153.40  4558.0 1151.07  4586.3 1151.61  4593.3 1149.91  4649.8 1148.79
  4678.1 1145.85  4685.3 1146.61  4809.3 1139.09  4918.6 1136.08  4953.9 1127.53
  4975.2 1128.46  4982.3 1127.27  4982.8 1126.77  5010.3 1127.27  5194.4 1132.77
  5300.5 1133.19  5385.2 1140.04  5435.7 1138.10  5455.9 1136.84  5583.3 1136.57
  5629.6 1138.96  5880.5 1151.61  6014.8 1153.22  6170.4 1161.08  6367.4 1167.94
#Mann=7,-1,0
  3981.9    0.05       0  4195.9    0.12       0  4809.3    0.05       0
  4982.3    0.05       0  5010.3    0.05       0  5435.7    0.12       0
  5629.6    0.05       0
Bank Sta=4982.3,5010.3
Exp/Cntr=0.3,0.1

Type RM Length L Ch R = 1,7180,430,430,430
BEGIN DESCRIPTION:
LEGION CREEK 13.0
END DESCRIPTION:
XS GIS Cut Line= 3
      2817655.69     10159703.11      2818244.75     10159079.00
      2818605.70     10158353.09
#Sta/Elev= 30
  4141.8 1154.54  4417.5 1143.59  4460.0 1143.45  4481.4 1141.65  4516.6 1141.91
  4650.9 1134.09  4672.4 1130.22  4721.7 1135.10  4799.8 1135.05  4814.0 1133.72
  4842.3 1126.44  4891.7 1126.27  4898.5 1125.28  4926.8 1126.96  4955.2 1124.92
  4998.6 1124.66  4999.1 1124.16  5026.8 1124.66  5073.6 1126.46  5085.5 1130.36
  5102.3 1131.51  5107.9 1133.51  5130.3 1136.24  5218.1 1137.20  5251.9 1137.97
  5296.9 1138.43  5348.7 1141.56  5475.6 1145.95  5707.1 1147.84  5810.7 1152.02
#Mann=5,-1,0
  4141.8    0.05       0  4998.6    0.03       0  5026.8    0.05       0
  5218.1    0.12       0  5251.9    0.05       0
Bank Sta=4998.6,5026.8
Exp/Cntr=0.3,0.1

Type RM Length L Ch R = 1,6750,648,648,648
BEGIN DESCRIPTION:
LEGION CREEK 12.0
END DESCRIPTION:
XS GIS Cut Line= 3
      2817905.71     10159703.10      2818814.39     10159256.22
      2819584.55     10158390.54
#Sta/Elev= 30
  4305.6 1149.04  4454.4 1142.86  4611.8 1134.11  4634.2 1132.42  4656.7 1128.50
  4707.2 1132.63  4729.7 1132.31  4752.2 1128.47  4814.0 1124.69  4948.9 1124.51
  4985.3 1122.65  4985.8 1122.15  5013.5 1122.65  5016.3 1125.34  5029.9 1130.35
  5044.3 1133.58  5120.3 1134.24  5173.6 1130.95  5224.1 1133.82  5241.0 1132.80
  5291.5 1134.99  5381.8 1135.09  5519.9 1137.24  5534.1 1135.77  5604.3 1138.67
  5690.8 1139.55  5884.6 1143.65  6001.5 1146.37  6220.6 1142.34  6476.9 1149.76
#Mann=7,-1,0
  4305.6    0.05       0  4985.3    0.03       0  5013.5    0.05       0
  5120.3    0.12       0  5381.8    0.05       0  5690.8    0.12       0
  5884.6    0.05       0
Bank Sta=4985.3,5013.5
Exp/Cntr=0.3,0.1

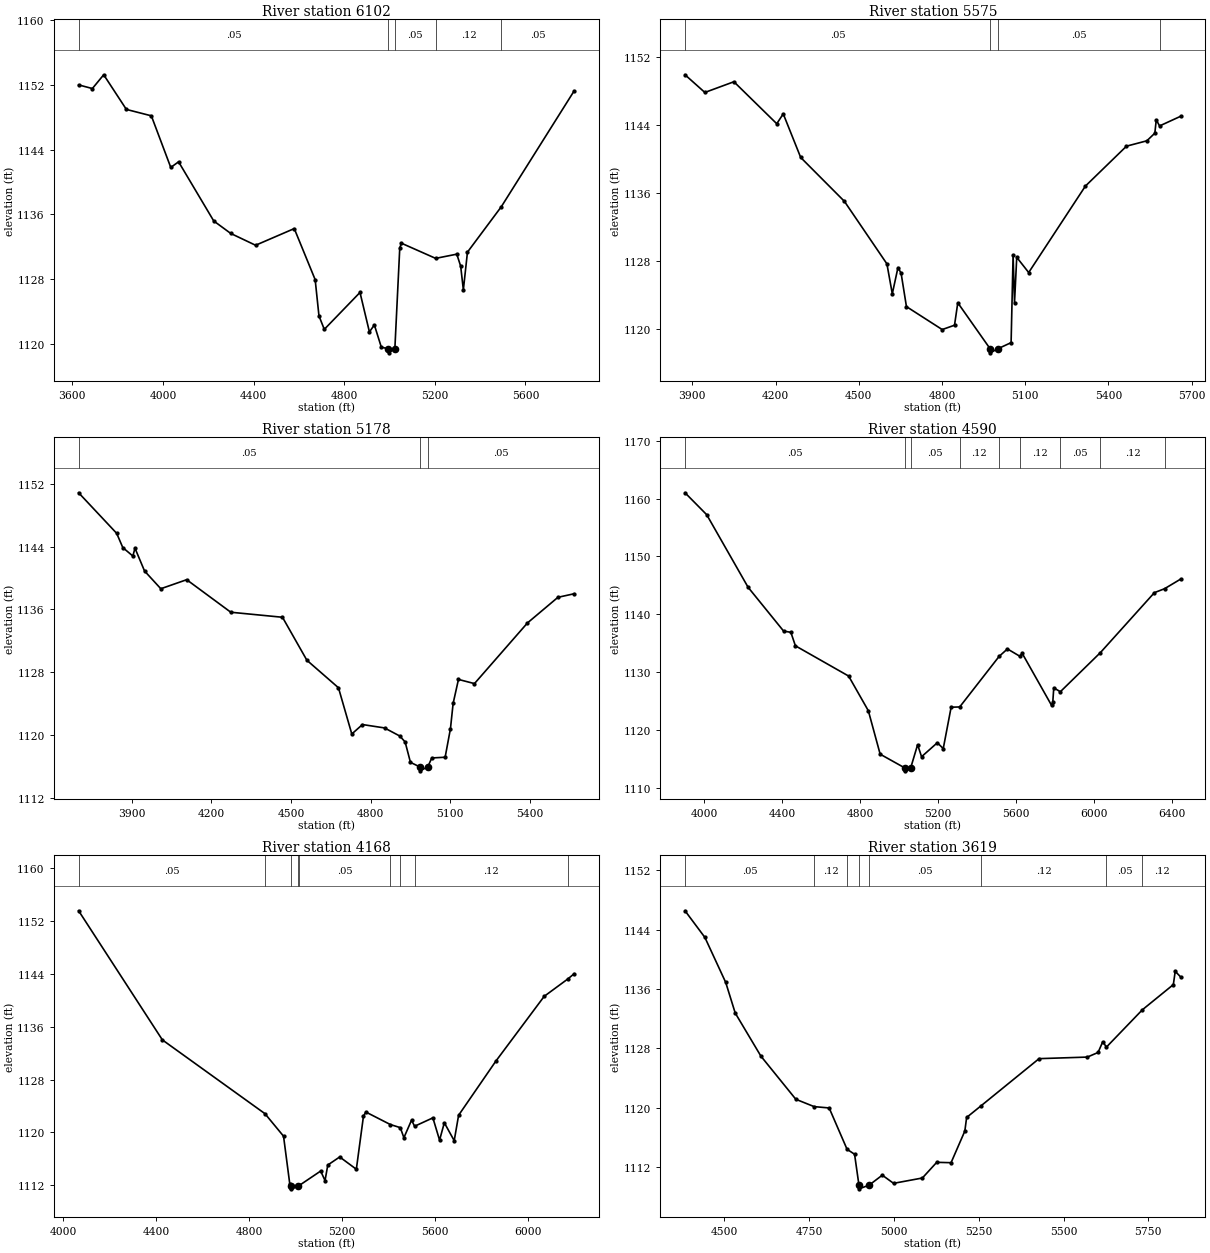
Type RM Length L Ch R = 1,6102,527,527,527
BEGIN DESCRIPTION:
LEGION CREEK 11.0
END DESCRIPTION:
XS GIS Cut Line= 3
      2817465.14     10160169.66      2818480.06     10160115.92
      2819555.68     10159653.11
#Sta/Elev= 30
  3627.8 1152.01  3688.4 1151.56  3738.5 1153.26  3838.6 1148.98  3948.8 1148.19
  4034.6 1141.81  4069.0 1142.51  4224.3 1135.20  4299.3 1133.66  4409.0 1132.20
  4579.7 1134.26  4672.0 1127.95  4688.8 1123.47  4712.3 1121.81  4869.9 1126.37
  4911.5 1121.49  4933.3 1122.36  4964.0 1119.61  4995.3 1119.41  4995.8 1118.91
  5023.8 1119.41  5045.5 1131.89  5053.1 1132.45  5203.9 1130.58  5297.2 1131.10
  5314.3 1129.62  5326.2 1126.70  5344.3 1131.35  5493.7 1136.96  5815.1 1151.26
#Mann=5,-1,0
  3627.8    0.05       0  4995.3    0.03       0  5023.8    0.05       0
  5203.9    0.12       0  5493.7    0.05       0
Bank Sta=4995.3,5023.8
Exp/Cntr=0.3,0.1

Type RM Length L Ch R = 1,5575,397,397,397
BEGIN DESCRIPTION:
LEGION CREEK 10.0
END DESCRIPTION:
XS GIS Cut Line= 3
      2817817.37     10160766.67      2818362.00     10160598.10
      2819554.68     10160360.70
#Sta/Elev= 30
  3873.7 1149.91  3945.2 1147.83  4049.9 1149.09  4204.4 1144.15  4227.8 1145.31
  4290.7 1140.18  4448.2 1135.02  4601.5 1127.66  4620.9 1124.14  4641.3 1127.22
  4652.6 1126.57  4671.9 1122.63  4800.8 1119.93  4845.2 1120.44  4857.0 1123.08
  4973.1 1117.69  4973.6 1117.19  5002.8 1117.69  5049.2 1118.39  5056.4 1128.70
  5061.5 1123.09  5069.5 1128.43  5112.6 1126.64  5317.0 1136.81  5465.2 1141.51
  5538.6 1142.14  5567.4 1143.04  5572.5 1144.61  5584.4 1143.89  5659.9 1145.02
#Mann=4,-1,0
  3873.7    0.05       0  4973.1    0.03       0  5002.8    0.05       0
  5584.4    0.12       0
Bank Sta=4973.1,5002.8
Exp/Cntr=0.3,0.1

Type RM Length L Ch R = 1,5178,588,588,588
BEGIN DESCRIPTION:
LEGION CREEK 9.0
END DESCRIPTION:
XS GIS Cut Line= 3
      2817650.25     10161298.00      2818468.30     10160920.97
      2819429.36     10160832.34
#Sta/Elev= 30
  3700.1 1150.84  3843.4 1145.68  3866.4 1143.87  3904.3 1142.79  3912.3 1143.79
  3948.3 1140.89  4009.6 1138.63  4107.0 1139.78  4273.2 1135.64  4467.8 1135.00
  4559.7 1129.53  4678.6 1126.03  4728.8 1120.15  4769.0 1121.35  4852.0 1120.92
  4909.5 1119.89  4929.6 1119.14  4949.7 1116.54  4985.0 1115.96  4985.5 1115.46
  5014.8 1115.96  5030.1 1117.10  5080.3 1117.19  5100.4 1120.84  5110.4 1124.04
  5130.5 1127.09  5190.7 1126.56  5390.4 1134.28  5505.1 1137.54  5566.0 1137.99
#Mann=3,-1,0
  3700.1    0.05       0  4985.0    0.03       0  5014.8    0.05       0
Bank Sta=4985,5014.8
Exp/Cntr=0.3,0.1

Type RM Length L Ch R = 1,4590,422,422,422
BEGIN DESCRIPTION:
LEGION CREEK 8.0
END DESCRIPTION:
XS GIS Cut Line= 3
      2817745.75     10161626.37      2819184.54     10161417.42
      2820235.26     10161142.80
#Sta/Elev= 30
  3902.2 1160.99  4013.3 1157.20  4225.5 1144.65  4407.4 1137.08  4444.7 1136.86
  4468.0 1134.53  4740.8 1129.30  4841.9 1123.30  4902.5 1115.79  5029.0 1113.41
  5029.5 1112.91  5058.9 1113.41  5094.5 1117.43  5114.7 1115.35  5195.6 1117.77
  5225.9 1116.76  5266.3 1123.91  5310.3 1123.96  5512.3 1132.70  5554.9 1133.99
  5618.6 1132.72  5630.7 1133.22  5781.0 1124.24  5787.3 1124.74  5792.4 1127.26
  5826.2 1126.59  6031.4 1133.35  6308.2 1143.72  6360.3 1144.40  6442.1 1146.05
#Mann=9,-1,0
  3902.2    0.05       0  5029.0    0.03       0  5058.9    0.05       0
  5310.3    0.12       0  5512.3    0.05       0  5618.6    0.12       0
  5826.2    0.05       0  6031.4    0.12       0  6360.3    0.05       0
Bank Sta=5029,5058.9
Exp/Cntr=0.3,0.1

Type RM Length L Ch R = 1,4168,549,549,549
BEGIN DESCRIPTION:
LEGION CREEK 7.0
END DESCRIPTION:
XS GIS Cut Line= 3
      2818038.24     10162181.61      2818730.81     10161918.91
      2820091.37     10161614.57
#Sta/Elev= 30
  4065.7 1153.51  4426.6 1133.99  4868.6 1122.84  4948.6 1119.44  4975.4 1112.24
  4982.2 1111.98  4982.7 1111.48  5012.1 1111.98  5017.2 1112.01  5108.6 1114.17
  5127.4 1112.73  5139.3 1115.08  5190.6 1116.30  5262.3 1114.44  5293.0 1122.47
  5303.3 1123.09  5408.8 1121.20  5451.7 1120.73  5467.2 1119.21  5500.2 1121.86
  5513.3 1120.94  5592.1 1122.21  5620.9 1118.84  5641.4 1121.47  5684.0 1118.76
  5702.9 1122.60  5862.7 1130.75  6071.8 1140.58  6174.2 1143.22  6200.6 1143.99
#Mann=9,-1,0
  4065.7    0.05       0  4868.6    0.12       0  4982.2    0.07       0
  5012.1    0.12       0  5017.2    0.05       0  5408.8    0.12       0
  5451.7    0.05       0  5513.3    0.12       0  6174.2    0.05       0
Bank Sta=4982.2,5012.1
Exp/Cntr=0.3,0.1

Type RM Length L Ch R = 1,3619,517,517,517
BEGIN DESCRIPTION:
LEGION CREEK 6.0
END DESCRIPTION:
XS GIS Cut Line= 3
      2818555.73     10162653.09      2819106.50     10162377.00
      2819905.67     10162103.12
#Sta/Elev= 30
  4383.9 1146.54  4442.5 1142.95  4503.9 1136.89  4531.9 1132.77  4607.6 1126.97
  4710.6 1121.16  4764.6 1120.17  4808.9 1119.99  4861.7 1114.42  4883.8 1113.76
  4896.7 1109.60  4897.2 1109.10  4926.8 1109.60  4965.5 1110.94  4998.8 1109.84
  5083.7 1110.56  5126.0 1112.67  5168.3 1112.62  5208.9 1116.88  5214.2 1118.71
  5256.7 1120.28  5427.8 1126.63  5570.0 1126.84  5601.7 1127.46  5615.5 1128.90
  5626.5 1128.19  5732.4 1133.21  5823.7 1136.60  5829.2 1138.39  5844.8 1137.65
#Mann=8,-1,0
  4383.9    0.05       0  4764.6    0.12       0  4861.7    0.05       0
  4896.7    0.03       0  4926.8    0.05       0  5256.7    0.12       0
  5626.5    0.05       0  5732.4    0.12       0
Bank Sta=4896.7,4926.8
Exp/Cntr=0.3,0.1