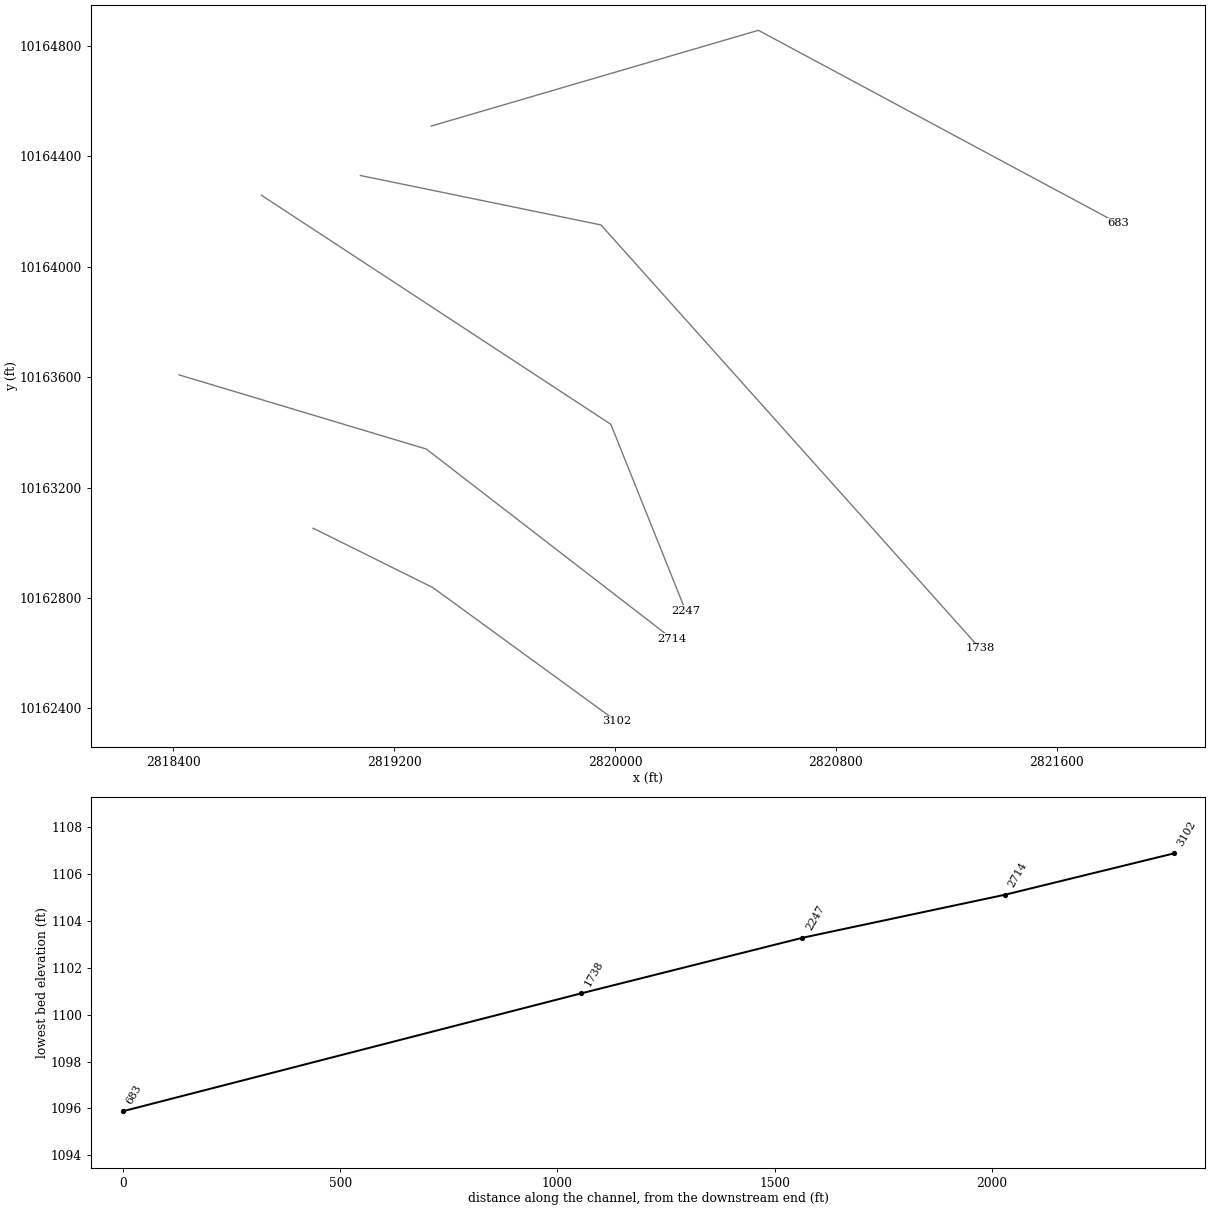
HEC-RAS study LEGION CREEK.prj: LEGION CREEK Base Level Engineering

--- LEGION CREEK.g01 (geometry) --- (continued)

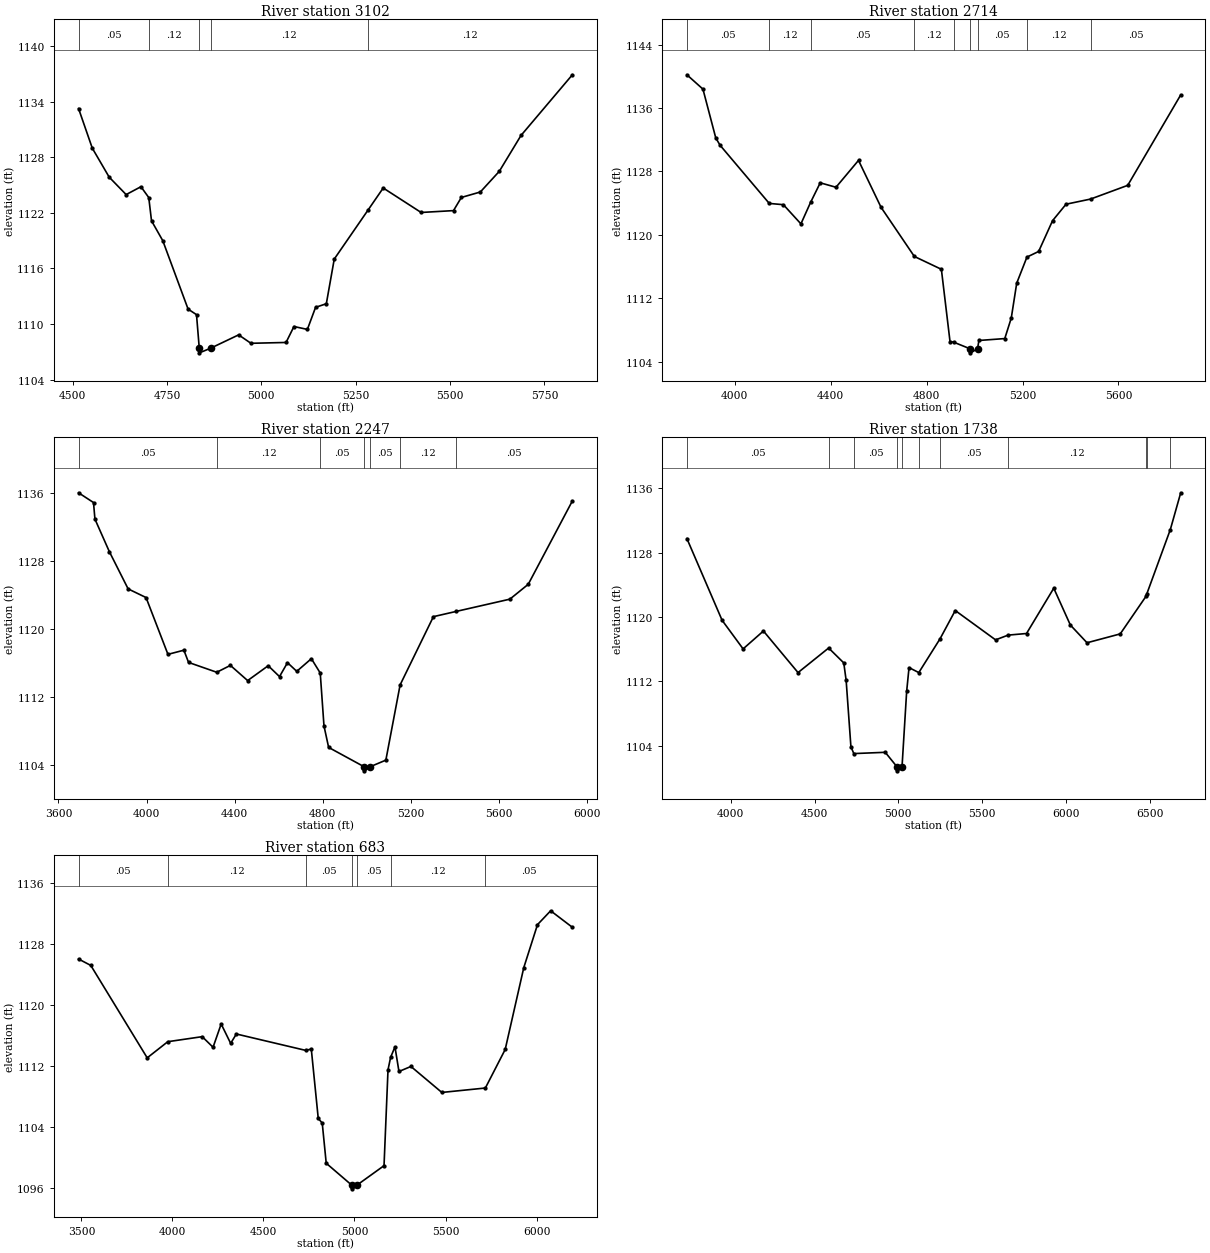
Type RM Length L Ch R = 1,3102,388,388,388
BEGIN DESCRIPTION:
LEGION CREEK 5.0
END DESCRIPTION:
XS GIS Cut Line= 3
      2818905.70     10163053.10      2819339.50     10162838.00
      2820005.71     10162353.09
#Sta/Elev= 30
  4515.8 1133.25  4552.2 1128.97  4597.0 1125.84  4641.9 1123.96  4681.1 1124.81
  4701.8 1123.64  4709.1 1121.13  4739.0 1118.98  4806.0 1111.60  4828.3 1111.00
  4835.6 1107.38  4836.1 1106.88  4865.7 1107.38  4939.9 1108.82  4972.5 1107.91
  5065.5 1108.00  5086.4 1109.72  5122.0 1109.41  5143.7 1111.79  5172.2 1112.18
  5193.2 1117.00  5282.7 1122.29  5322.9 1124.67  5423.3 1122.03  5509.1 1122.23
  5529.9 1123.65  5580.2 1124.24  5630.4 1126.47  5687.9 1130.34  5824.0 1136.89
#Mann=5,-1,0
  4515.8    0.05       0  4701.8    0.12       0  4835.6    0.03       0
  4865.7    0.12       0  5282.7    0.12       0
Bank Sta=4835.6,4865.7
Exp/Cntr=0.3,0.1

Type RM Length L Ch R = 1,2714,467,467,467
BEGIN DESCRIPTION:
LEGION CREEK 4.0
END DESCRIPTION:
XS GIS Cut Line= 3
      2818420.35     10163608.47      2819315.88     10163339.81
      2820205.66     10162653.13
#Sta/Elev= 30
  3800.7 1140.20  3867.6 1138.39  3921.1 1132.23  3939.0 1131.31  4144.1 1123.97
  4203.0 1123.81  4276.1 1121.39  4316.2 1124.09  4356.6 1126.57  4422.3 1126.01
  4516.2 1129.40  4610.2 1123.48  4749.0 1117.28  4861.7 1115.66  4897.7 1106.55
  4912.6 1106.47  4982.3 1105.62  4982.8 1105.12  5012.4 1105.62  5018.2 1106.68
  5126.0 1106.92  5153.1 1109.51  5175.8 1113.91  5218.4 1117.20  5267.2 1117.91
  5325.2 1121.79  5381.4 1123.87  5483.7 1124.52  5638.6 1126.25  5859.6 1137.66
#Mann=9,-1,0
  3800.7    0.05       0  4144.1    0.12       0  4316.2    0.05       0
  4749.0    0.12       0  4912.6    0.05       0  4982.3    0.03       0
  5012.4    0.05       0  5218.4    0.12       0  5483.7    0.05       0
Bank Sta=4982.3,5012.4
Exp/Cntr=0.3,0.1

Type RM Length L Ch R = 1,2247,509,509,509
BEGIN DESCRIPTION:
LEGION CREEK 3.0
END DESCRIPTION:
XS GIS Cut Line= 3
      2818718.91     10164259.18      2819984.54     10163429.36
      2820255.68     10162753.11
#Sta/Elev= 30
  3691.3 1136.03  3759.2 1134.88  3765.7 1132.93  3830.9 1129.11  3916.4 1124.71
  3997.8 1123.69  4097.2 1117.00  4169.6 1117.49  4190.7 1116.05  4318.8 1114.89
  4380.7 1115.70  4459.0 1113.91  4552.4 1115.66  4603.7 1114.38  4639.9 1116.02
  4682.0 1115.00  4748.4 1116.49  4788.6 1114.80  4805.6 1108.57  4826.7 1106.04
  4986.6 1103.78  4987.1 1103.28  5016.7 1103.78  5086.5 1104.54  5151.2 1113.40
  5302.4 1121.44  5406.4 1122.06  5649.5 1123.50  5732.9 1125.25  5933.3 1135.07
#Mann=7,-1,0
  3691.3    0.05       0  4318.8    0.12       0  4788.6    0.05       0
  4986.6    0.05       0  5016.7    0.05       0  5151.2    0.12       0
  5406.4    0.05       0
Bank Sta=4986.6,5016.7
Exp/Cntr=0.3,0.1

Type RM Length L Ch R = 1,1738,1055,1055,1055
BEGIN DESCRIPTION:
LEGION CREEK 2.0
END DESCRIPTION:
XS GIS Cut Line= 3
      2819077.06     10164330.85      2819948.72     10164151.75
      2821320.98     10162618.40
#Sta/Elev= 30
  3738.3 1129.73  3948.4 1119.59  4073.8 1116.04  4195.1 1118.26  4401.7 1113.10
  4584.4 1116.15  4674.7 1114.30  4688.9 1112.12  4717.3 1103.90  4734.6 1103.05
  4922.2 1103.21  4992.3 1101.41  4992.8 1100.91  5022.4 1101.41  5050.0 1110.76
  5064.2 1113.72  5122.5 1113.10  5249.5 1117.30  5340.1 1120.80  5580.8 1117.16
  5655.7 1117.75  5765.5 1117.95  5928.1 1123.57  6027.2 1119.00  6126.6 1116.80
  6324.8 1117.90  6478.2 1122.55  6482.7 1122.82  6623.9 1130.85  6685.9 1135.41
#Mann=11,-1,0
  3738.3    0.05       0  4584.4    0.12       0  4734.6    0.05       0
  4992.3    0.03       0  5022.4    0.05       0  5122.5    0.12       0
  5249.5    0.05       0  5655.7    0.12       0  6478.2    0.05       0
  6482.7    0.12       0  6623.9    0.05       0
Bank Sta=4992.3,5022.4
Exp/Cntr=0.3,0.1

Type RM Length L Ch R = 1,683,0,0,0
BEGIN DESCRIPTION:
LEGION CREEK 1.0
END DESCRIPTION:
XS GIS Cut Line= 3
      2819333.80     10164509.96      2820518.99     10164856.86
      2821820.85     10164158.20
#Sta/Elev= 30
  3484.4 1126.04  3551.6 1125.20  3861.5 1113.07  3974.6 1115.19  4163.6 1115.85
  4223.2 1114.46  4267.8 1117.51  4319.9 1114.97  4351.2 1116.20  4731.9 1114.05
  4762.8 1114.22  4801.0 1105.12  4822.9 1104.51  4844.8 1099.24  4984.2 1096.38
  4984.7 1095.88  5014.4 1096.38  5162.3 1098.92  5184.2 1111.50  5198.3 1113.13
  5222.4 1114.51  5244.3 1111.28  5310.1 1111.94  5479.8 1108.53  5718.9 1109.11
  5827.8 1114.17  5929.9 1124.91  6005.2 1130.55  6077.5 1132.37  6196.8 1130.20
#Mann=7,-1,0
  3484.4    0.05       0  3974.6    0.12       0  4731.9    0.05       0
  4984.2    0.03       0  5014.4    0.05       0  5198.3    0.12       0
  5718.9    0.05       0
Bank Sta=4984.2,5014.4
Exp/Cntr=0.3,0.1

Chan Stop Cuts=-1