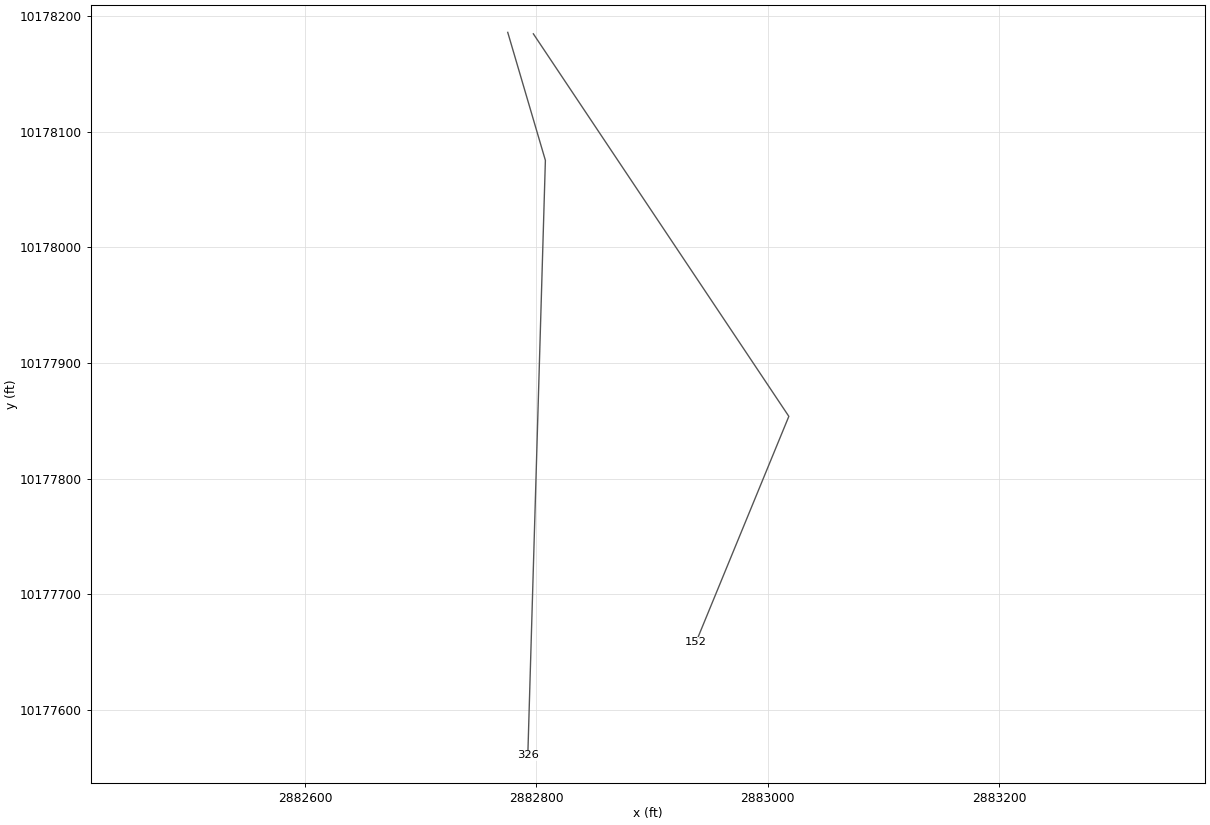
HEC-RAS study LIME HOLLOW CREEK.prj: LIME HOLLOW CREEK Base Level Engineering

--- LIME HOLLOW CREEK.g01 (geometry) --- (continued)

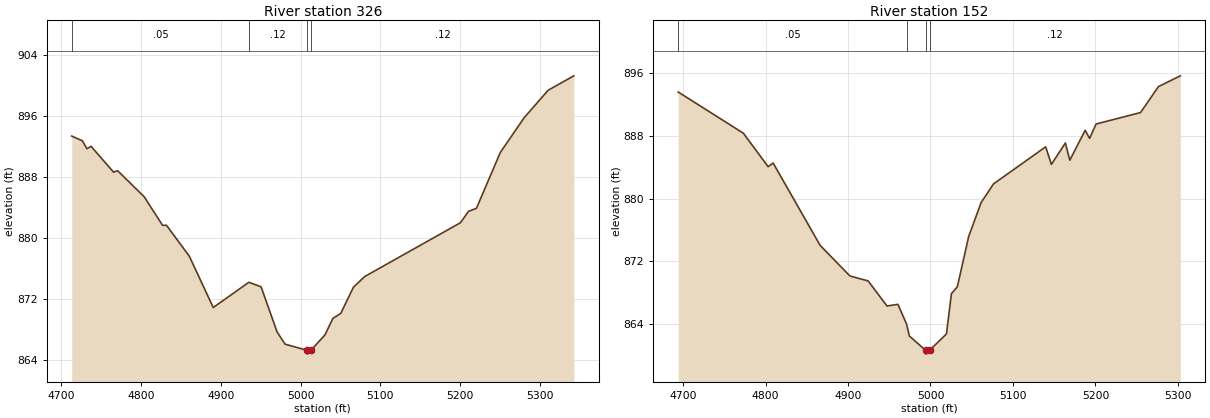
Type RM Length L Ch R = 1 ,326     ,174,174,174
BEGIN DESCRIPTION:
Mapping XS 8afc43c5
END DESCRIPTION:
XS GIS Cut Line= 3
      2882775.18     10178185.91      2882807.73     10178075.24
      2882792.54     10177560.92
#Sta/Elev= 30
  4712.9  893.42  4726.2   892.8  4731.9  891.76  4737.1  892.08  4765.3  888.69
  4770.5  888.87  4803.8  885.45  4826.8  881.71  4831.8  881.71  4860.4  877.65
  4890.4  870.92  4935.1  874.23  4950.4  873.64  4970.5  867.71  4980.5  866.11
    5008   865.3  5008.3   864.8    5013   865.3  5030.5  867.32  5040.5  869.49
  5050.5  870.16  5066.3  873.59  5080.5  874.99  5200.6  882.05  5210.6  883.54
  5220.6  883.94  5250.6  891.28  5280.6  895.85  5310.6  899.44  5342.8  901.33
#Mann= 4 ,-1 , 0
  4712.9     .05       0  4935.1     .12       0    5008     .07       0
    5013     .12       0
Bank Sta=5008,5013
XS Rating Curve= 0 ,0
Exp/Cntr=0.3,0.1

Type RM Length L Ch R = 1 ,152     ,0,0,0
BEGIN DESCRIPTION:
LIME HOLLOW CREEK 1.0
END DESCRIPTION:
XS GIS Cut Line= 3
      2882797.34     10178184.63      2883018.24     10177853.88
      2882937.94     10177658.58
#Sta/Elev= 30
  4694.1  893.54  4773.1   888.3  4803.1  884.05  4809.2  884.51  4866.2  874.04
  4902.3  870.15  4924.4  869.52  4947.3  866.33  4960.5  866.54    4971  864.04
  4974.4  862.51    4994  860.71  4994.4  860.21  4999.1  860.71  5019.4  862.78
  5025.4  867.89  5032.6  868.78  5046.4  875.19  5061.5   879.5  5076.5  881.86
  5139.7  886.57  5146.7  884.34  5163.6  887.06    5169  884.87  5187.6  888.67
    5193  887.65  5200.8  889.47  5254.8  890.93  5276.5  894.23    5303   895.6
#Mann= 4 ,-1 , 0
  4694.1     .05       0    4971     .12       0    4994     .07       0
  4999.1     .12       0
Bank Sta=4994,4999.1
XS Rating Curve= 0 ,0
Exp/Cntr=0.3,0.1

Chan Stop Cuts=-1
Use User Specified Reach Order=0
Composite Channel Slope=5