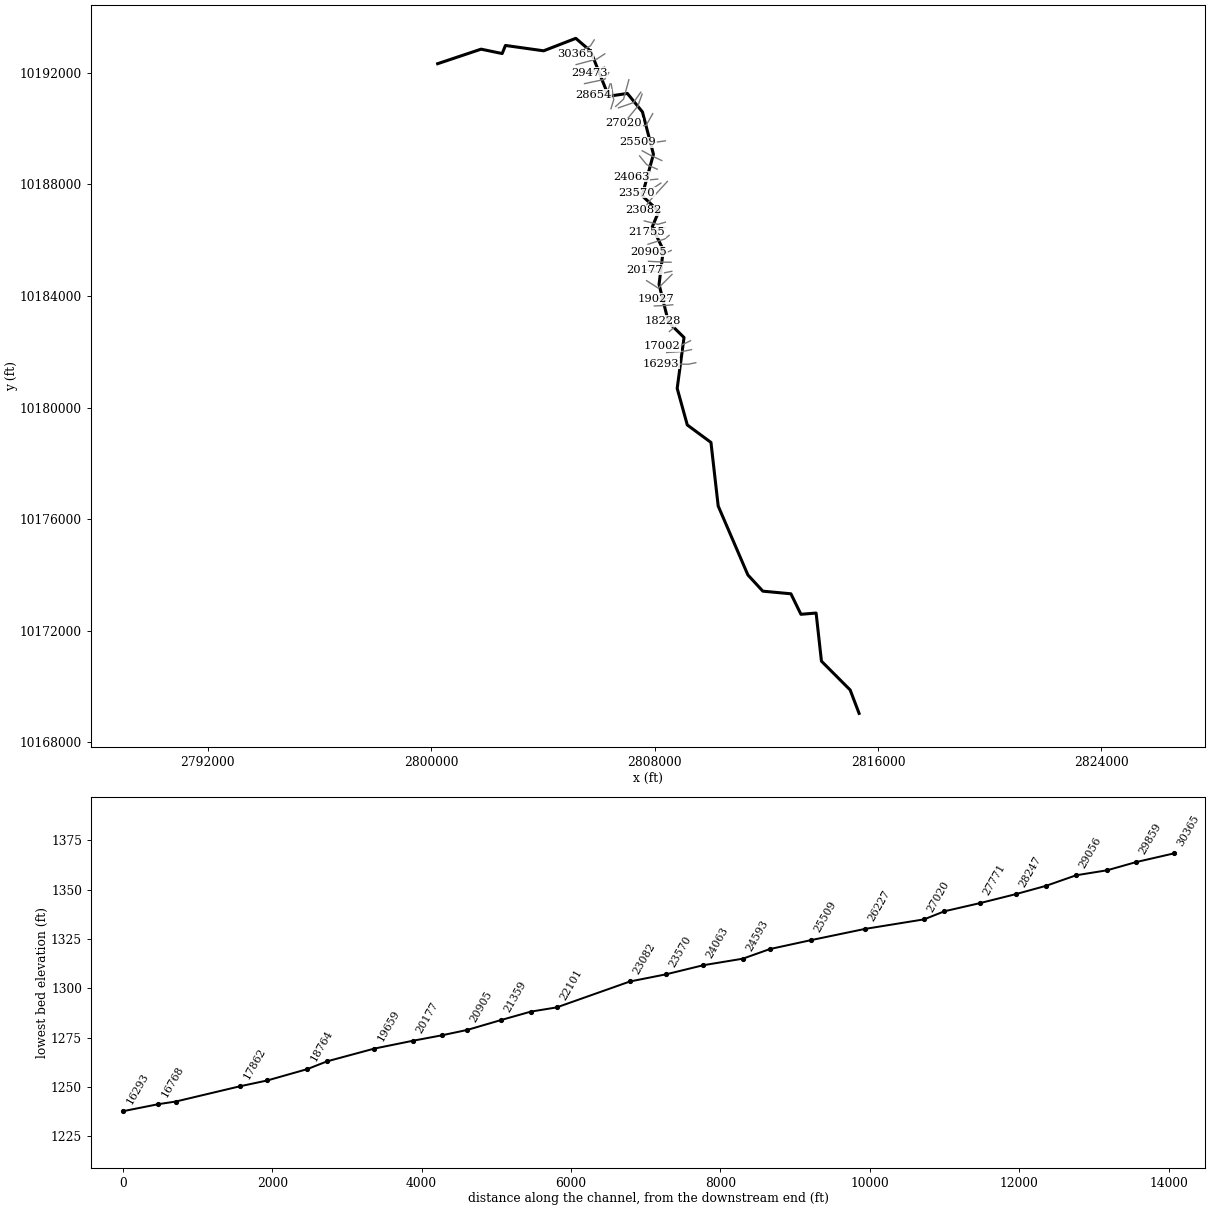
--- LOST HOLLOW CREEK.prj (project) ---

Proj Title=LOST HOLLOW CREEK Base Level Engineering
Current Plan=p01
Default Exp/Contr=0.3,0.1
English Units
Geom File=g01
Flow File=f01
Plan File=p01
Y Axis Title=Elevation
X Axis Title(PF)=Main Channel Distance
X Axis Title(XS)=Station
BEGIN DESCRIPTION:
LOST HOLLOW CREEK
END DESCRIPTION:
DSS Export Rating Curves= 0
DSS Export Rating Curve Sorted= 0
DSS Export Volume Flow Curves= 0
DXF OffsetX= 0
DXF OffsetY= 0
DXF ScaleX= 1
DXF ScaleY= 10

--- LOST HOLLOW CREEK.p01 (plan) ---

Plan Title=Multiple Run
Short Identifier=Multiple
Geom File=g01
Flow File=f01
Subcritical Flow
K Sum by GR= 0
Std Step Tol= 0.01
Critical Tol= 0.01
Num of Std Step Trials= 20
Max Error Tol= 0.3
Flow Tol Ratio= 0.001
Split Flow NTrial= 30
Split Flow Tol= 0.02
Split Flow Ratio= 0.02
Log Output Level= 0
Friction Slope Method= 1
Unsteady Friction Slope Method= 2
Unsteady Bridges Friction Slope Method= 1
Parabolic Critical Depth
Global Vel Dist=  1 , 1 , 1
Global Log Level= 0
CheckData=True
Encroach Param= -1, 0, 0, 0
BEGIN DESCRIPTION:
Multiple Run
END DESCRIPTION:

--- LOST HOLLOW CREEK.f01 (steady flow) ---

Flow Title=Multiple
Number of Profiles=7
Profile Names=10-year,25-year,50-year,1pct_min,100-year,1pct_plu,500-year
River Rch & RM= LOST HOLLOW CREE,Reach-1,30365
     418     675    1181     929    1624    2836    2310
River Rch & RM= LOST HOLLOW CREE,Reach-1,29473
     752    1265    2156    1577    3011    5749    4256
River Rch & RM= LOST HOLLOW CREE,Reach-1,22101
     966    1656    2793    1968    3934    7866    5564
River Rch & RM= LOST HOLLOW CREE,Reach-1,17002
    1527    2693    4754    3311    6806   13991    9582
River Rch & RM= LOST HOLLOW CREE,Reach-1,9425
    1868    3347    5853    3962    8439   17975   11890
River Rch & RM= LOST HOLLOW CREE,Reach-1,1453
    1926    3462    6021    4055    8687   18612   12238
Boundary for River Rch & Prof#=LOST HOLLOW CREE,Reach-1,1
Up Type=0
Dn Type=3
Dn Slope=0.005
Boundary for River Rch & Prof#=LOST HOLLOW CREE,Reach-1,2
Up Type=0
Dn Type=3
Dn Slope=0.005
Boundary for River Rch & Prof#=LOST HOLLOW CREE,Reach-1,3
Up Type=0
Dn Type=3
Dn Slope=0.005
Boundary for River Rch & Prof#=LOST HOLLOW CREE,Reach-1,4
Up Type=0
Dn Type=3
Dn Slope=0.005
Boundary for River Rch & Prof#=LOST HOLLOW CREE,Reach-1,5
Up Type=0
Dn Type=3
Dn Slope=0.005
Boundary for River Rch & Prof#=LOST HOLLOW CREE,Reach-1,6
Up Type=0
Dn Type=3
Dn Slope=0.005
Boundary for River Rch & Prof#=LOST HOLLOW CREE,Reach-1,7
Up Type=0
Dn Type=3
Dn Slope=0.005

--- LOST HOLLOW CREEK.g01 (geometry) ---

Geom Title=Existing Conditions
Program Version=4.10

River Reach=LOST HOLLOW CREE,Reach-1
Reach XY= 30
      2800230.25       10192323.       2801785.5       10192844.
        2802542.       10192687.        2802658.       10192977.
        2804025.       10192785.       2805177.5       10193232.
        2805710.       10192772.        2806352.       10191157.
      2807024.75       10191257.      2807564.25       10190594.
       2807957.5       10189078.      2807551.25       10187593.
      2808149.75       10187036.        2807914.       10186472.
      2808310.25       10185650.        2808159.       10184414.
      2808495.75       10183061.       2809052.5       10182512.
      2808807.75       10180688.       2809169.5       10179378.
        2810017.       10178752.      2810275.75       10176474.
       2811339.5       10174003.       2811874.5       10173422.
      2812880.25       10173328.       2813238.5       10172593.
        2813782.       10172639.      2813973.25       10170914.
       2815001.5       10169882.       2815320.5       10169043.

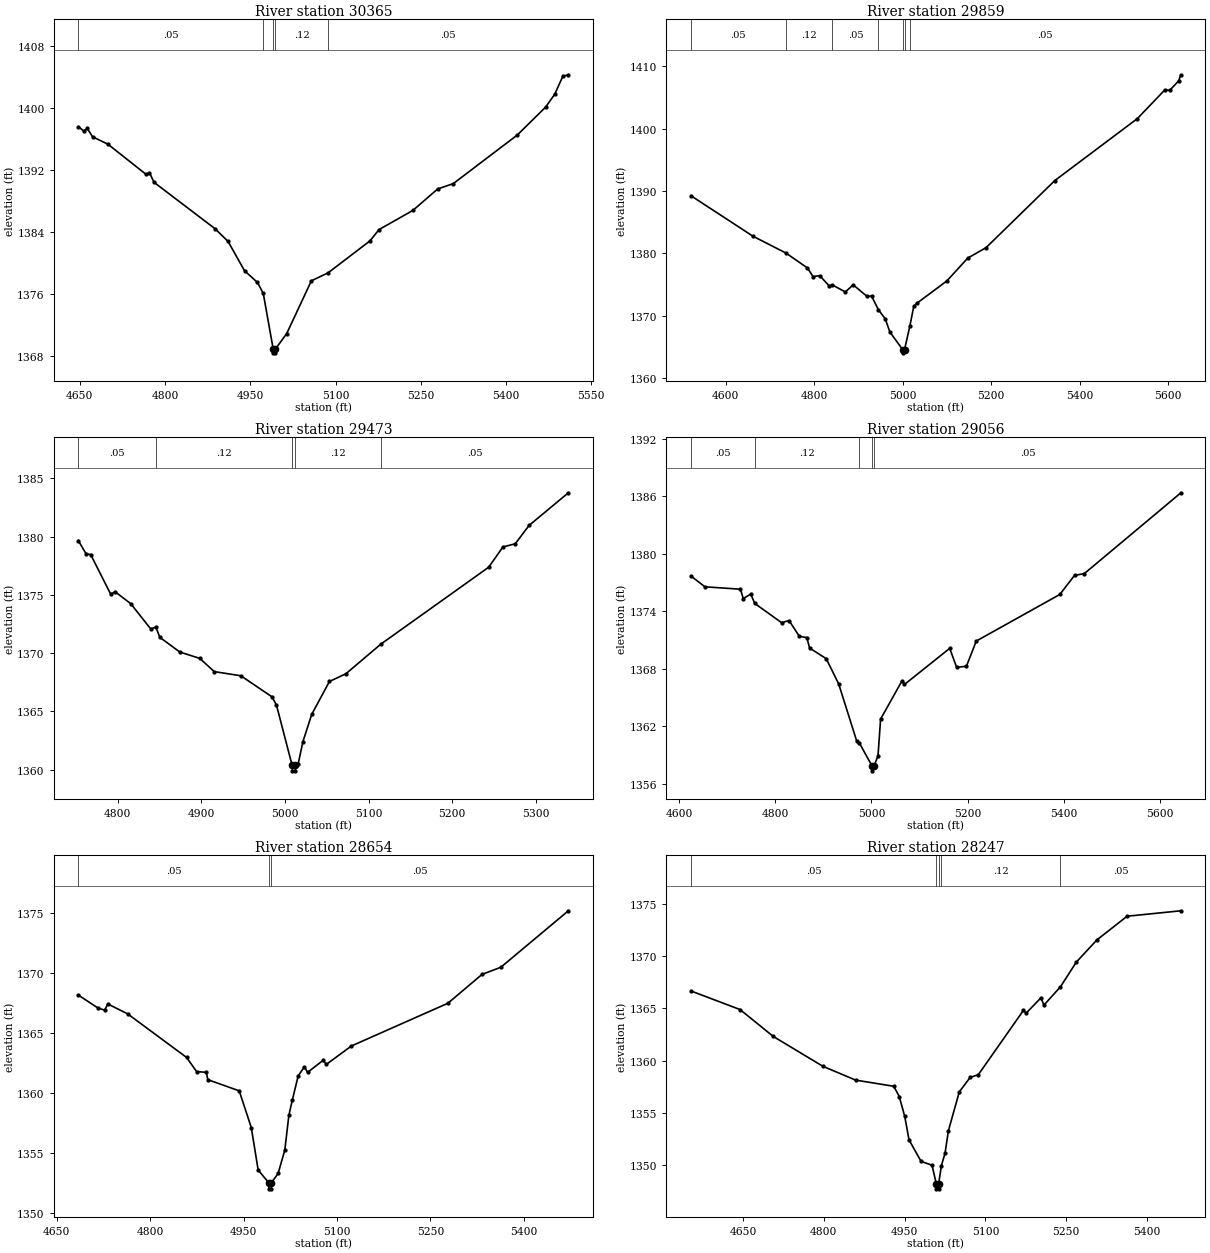
Type RM Length L Ch R = 1 ,30365   ,506,506,506
BEGIN DESCRIPTION:
LOST HOLLOW CREEK 67.0
END DESCRIPTION:
XS GIS Cut Line= 3
      2805836.21     10193175.74      2805703.41     10192964.82
       2805167.1     10192668.03
#Sta/Elev= 30
  4647.5 1397.59  4657.2 1397.01  4663.1 1397.36  4672.5 1396.28  4699.6 1395.32
  4766.7 1391.43  4772.6 1391.66  4780.6 1390.41    4888 1384.43  4910.9 1382.79
  4939.9 1379.01  4962.7  1377.5  4972.9 1376.08  4990.3 1368.93  4990.5 1368.43
    4994 1368.43  4994.3 1368.93    5014  1370.9  5057.5 1377.71  5086.9 1378.74
  5160.6 1382.86  5176.6 1384.32  5236.2 1386.79  5279.7 1389.55  5307.2 1390.24
  5419.9 1396.51  5469.8 1400.11  5485.8 1401.78  5499.9 1404.07  5509.7 1404.27
#Mann= 5 ,-1 , 0
  4647.5     .05       0  4972.9     .12       0  4990.3     .07       0
  4994.3     .12       0  5086.9     .05       0
Bank Sta=4990.3,4994.3
XS Rating Curve= 0 ,0
Exp/Cntr=0.3,0.1

Type RM Length L Ch R = 1 ,29859   ,386,386,386
BEGIN DESCRIPTION:
LOST HOLLOW CREEK 66.0
END DESCRIPTION:
XS GIS Cut Line= 3
      2806216.44     10192675.76      2805929.16     10192489.22
      2805190.49     10192290.37
#Sta/Elev= 30
  4521.7 1389.24    4662 1382.74  4736.3 1380.05  4784.9 1377.66  4797.8 1376.27
    4813 1376.41  4834.1 1374.78  4841.7 1374.91  4870.8  1373.8  4888.5 1374.94
  4919.6  1373.1    4930 1373.14  4945.4 1370.96    4961 1369.47  4971.4 1367.37
  5000.5 1364.53  5000.7 1364.03  5004.5 1364.53  5016.4 1368.27  5025.4 1371.48
  5033.5 1372.04  5100.1 1375.56  5147.4 1379.23  5188.9 1380.91  5344.2 1391.67
  5530.6  1401.6  5592.8 1406.21  5603.8 1406.14  5623.8 1407.64  5629.2 1408.64
#Mann= 7 ,-1 , 0
  4521.7     .05       0  4736.3     .12       0  4841.7     .05       0
  4945.4     .12       0  5000.5     .07       0  5004.5     .12       0
  5016.4     .05       0
Bank Sta=5000.5,5004.5
XS Rating Curve= 0 ,0
Exp/Cntr=0.3,0.1

Type RM Length L Ch R = 1 ,29473   ,417,417,417
BEGIN DESCRIPTION:
LOST HOLLOW CREEK 65.0
END DESCRIPTION:
XS GIS Cut Line= 3
      2806205.69     10192203.12      2806044.55     10192136.69
      2805655.65      10192003.1
#Sta/Elev= 30
  4753.2 1379.65  4762.5 1378.51  4767.9 1378.46  4791.8 1375.06  4797.2 1375.26
  4815.8 1374.24  4839.7 1372.07  4845.8 1372.22  4850.6 1371.35  4874.4 1370.09
  4898.4 1369.54  4915.5 1368.41  4947.4 1368.05  4984.6 1366.24  4989.9 1365.54
  5008.5 1360.39  5008.8 1359.89  5012.3 1359.89  5012.5 1360.39  5015.8 1360.47
  5021.5 1362.39    5032 1364.73  5053.2 1367.56    5073 1368.23  5114.5 1370.76
  5243.5 1377.37  5260.5 1379.11  5275.2 1379.38  5291.8 1380.96  5338.7 1383.76
#Mann= 5 ,-1 , 0
  4753.2     .05       0  4845.8     .12       0  5008.5     .07       0
  5012.5     .12       0  5114.5     .05       0
Bank Sta=5008.5,5012.5
XS Rating Curve= 0 ,0
Exp/Cntr=0.3,0.1

Type RM Length L Ch R = 1 ,29056   ,402,402,402
BEGIN DESCRIPTION:
LOST HOLLOW CREEK 64.0
END DESCRIPTION:
XS GIS Cut Line= 3
       2806355.7     10192003.13      2806211.22     10191761.69
      2805489.17     10191608.45
#Sta/Elev= 30
  4624.5 1377.67  4653.7 1376.54  4727.6 1376.29  4733.4 1375.32    4749 1375.77
  4757.5  1374.8  4813.2  1372.8  4828.7 1373.02  4850.1 1371.38  4865.7 1371.24
  4871.5 1370.15  4905.9 1369.05    4932 1366.41  4969.5 1360.44  4974.8 1360.26
  5001.5 1357.84  5001.8 1357.34  5005.5 1357.84  5013.8 1358.92  5019.2 1362.74
  5063.7 1366.73  5068.8 1366.35    5163 1370.12  5177.3 1368.14  5197.8 1368.25
  5218.2 1370.88    5392 1375.74  5422.7 1377.73  5443.1 1377.92    5644 1386.35
#Mann= 5 ,-1 , 0
  4624.5     .05       0  4757.5     .12       0  4974.8     .05       0
  5001.5     .05       0  5005.5     .05       0
Bank Sta=5001.5,5005.5
XS Rating Curve= 0 ,0
Exp/Cntr=0.3,0.1

Type RM Length L Ch R = 1 ,28654   ,407,407,407
BEGIN DESCRIPTION:
LOST HOLLOW CREEK 63.0
END DESCRIPTION:
XS GIS Cut Line= 3
      2806405.68     10191603.09      2806339.21     10191403.93
      2805800.18     10191199.35
#Sta/Elev= 30
  4684.9 1368.15  4716.5 1367.07    4727  1366.9  4732.3 1367.41  4763.9 1366.59
  4858.7 1362.95  4874.6 1361.78  4890.3 1361.71  4892.7  1361.1  4943.1 1360.17
  4962.5  1357.1  4973.5 1353.57  4990.6  1352.5  4990.9    1352  4994.5    1352
  4994.7  1352.5  5005.6 1353.29  5016.3 1355.24  5022.8 1358.13  5028.2 1359.37
  5037.7 1361.41  5047.6 1362.17  5052.9 1361.71  5077.7 1362.71  5083.1 1362.38
  5123.2 1363.91    5278 1367.47  5332.9 1369.88    5363 1370.47  5471.4 1375.18
#Mann= 3 ,-1 , 0
  4684.9     .05       0  4990.6     .05       0  4994.7     .05       0
Bank Sta=4990.6,4994.7
XS Rating Curve= 0 ,0
Exp/Cntr=0.3,0.1

Type RM Length L Ch R = 1 ,28247   ,476,476,476
BEGIN DESCRIPTION:
LOST HOLLOW CREEK 62.0
END DESCRIPTION:
XS GIS Cut Line= 3
       2806445.6     10191594.99       2806535.9     10191036.05
      2806435.36     10190707.59
#Sta/Elev= 30
  4553.2 1366.67  4644.5 1364.89  4706.2 1362.32  4798.2 1359.47    4859 1358.15
  4929.9 1357.56    4940 1356.58  4950.2 1354.68  4958.2 1352.43  4980.6 1350.38
  5000.8 1350.02  5008.7 1348.26    5009 1347.76  5012.9 1347.76  5013.2 1348.26
  5018.2 1349.97  5025.1 1351.19  5031.2  1353.3  5051.5 1357.03  5071.7 1358.41
  5086.8 1358.67  5170.5 1364.81  5175.7 1364.55  5203.2 1366.02  5208.5 1365.31
  5239.2 1367.06  5268.8 1369.43  5306.8 1371.54    5363 1373.81  5462.9 1374.33
#Mann= 5 ,-1 , 0
  4553.2     .05       0  5008.7     .05       0  5013.2     .05       0
  5018.2     .12       0  5239.2     .05       0
Bank Sta=5008.7,5013.2
XS Rating Curve= 0 ,0
Exp/Cntr=0.3,0.1

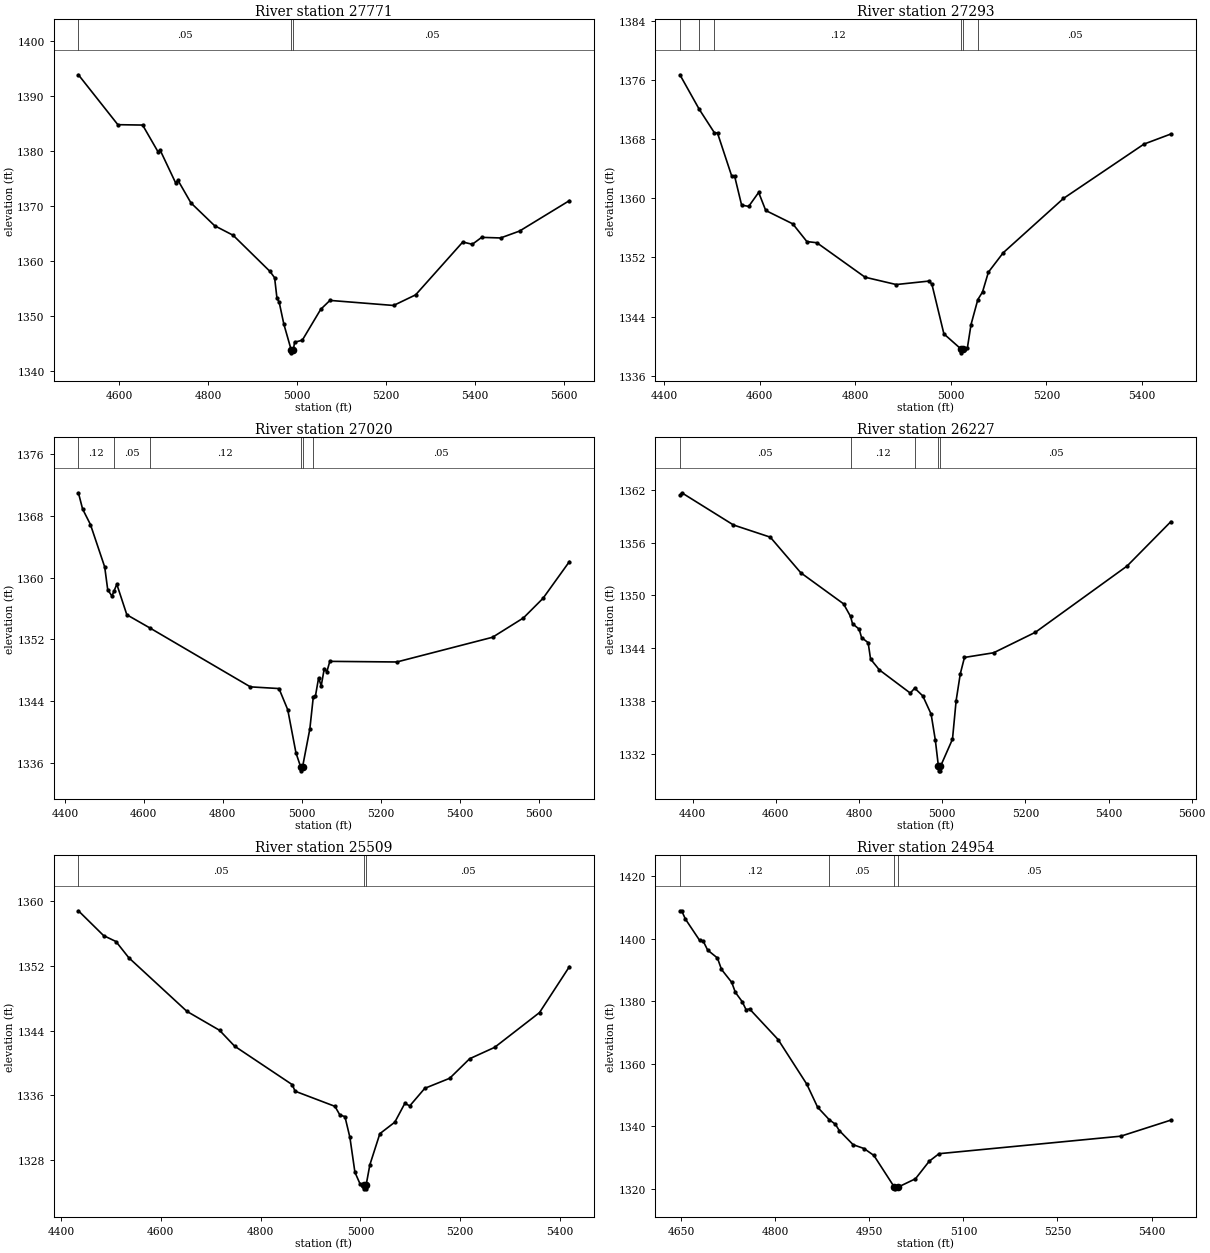
Type RM Length L Ch R = 1 ,27771   ,478,478,478
BEGIN DESCRIPTION:
LOST HOLLOW CREEK 61.0
END DESCRIPTION:
XS GIS Cut Line= 3
      2807078.42     10191748.71       2806888.3     10191053.36
      2806607.03     10190792.92
#Sta/Elev= 30
  4508.5 1393.79  4597.2 1384.72  4652.9 1384.65  4687.4 1379.81  4692.6 1380.04
  4727.1 1374.15  4732.3 1374.62  4761.6  1370.5  4814.9 1366.35  4856.4 1364.62
  4939.4 1358.04  4949.7  1356.9  4954.9 1353.25  4960.1 1352.41  4970.5 1348.46
  4987.1 1343.75  4987.4 1343.25  4991.8 1343.75  4994.6 1345.18  5011.9 1345.54
  5053.4 1351.16  5074.1 1352.78  5217.2 1351.86  5266.8 1353.79  5372.8 1363.39
  5394.3 1362.98  5415.3 1364.24  5457.8 1364.13  5500.4 1365.38  5612.7 1370.92
#Mann= 3 ,-1 , 0
  4508.5     .05       0  4987.1     .05       0  4991.8     .05       0
Bank Sta=4987.1,4991.8
XS Rating Curve= 0 ,0
Exp/Cntr=0.3,0.1

Type RM Length L Ch R = 1 ,27293   ,273,273,273
BEGIN DESCRIPTION:
LOST HOLLOW CREEK 60.0
END DESCRIPTION:
XS GIS Cut Line= 3
      2807505.66     10191303.08      2807239.87     10190928.36
       2806703.4     10190740.86
#Sta/Elev= 30
    4433 1376.67  4473.3 1372.02    4505 1368.85  4511.7 1368.79  4541.2 1363.02
  4547.4 1362.99  4562.1 1359.06  4576.9 1358.88  4597.8 1360.77  4612.6 1358.33
  4669.2 1356.52  4698.7 1354.13  4719.6 1353.97  4820.5 1349.31  4885.7 1348.32
  4954.4 1348.79  4960.4 1348.36  4985.5 1341.65  5021.6 1339.59    5022 1339.09
  5026.3 1339.59  5034.6 1339.74  5042.3 1342.92  5056.5 1346.29  5066.3 1347.31
  5078.6 1349.99  5109.7 1352.62  5235.8 1359.96  5404.2  1367.3  5460.7 1368.67
#Mann= 6 ,-1 , 0
    4433     .12       0  4473.3     .05       0    4505     .12       0
  5021.6     .07       0  5026.3     .12       0  5056.5     .05       0
Bank Sta=5021.6,5026.3
XS Rating Curve= 0 ,0
Exp/Cntr=0.3,0.1

Type RM Length L Ch R = 1 ,27020   ,793,793,793
BEGIN DESCRIPTION:
LOST HOLLOW CREEK 59.0
END DESCRIPTION:
XS GIS Cut Line= 3
      2807552.37     10191233.07      2807396.12     10190798.15
      2806899.95     10190194.02
#Sta/Elev= 30
  4434.3 1370.98  4444.9 1368.88  4464.8 1366.87  4500.9 1361.38  4508.6 1358.42
  4519.3 1357.61  4524.1 1358.21  4531.6 1359.14    4557 1355.19  4614.8  1353.5
  4869.9 1345.86  4942.4 1345.64  4964.6  1342.9  4985.4 1337.32  4997.4 1335.49
  4997.8 1334.99  5002.1 1335.49  5020.6 1340.42  5029.3 1344.54  5034.9 1344.71
  5042.8 1347.03  5049.3 1345.98  5057.2 1348.23  5063.6 1347.81  5071.2 1349.16
  5240.9 1349.08  5483.4 1352.28  5561.6 1354.78  5611.1 1357.31  5678.2 1362.08
#Mann= 6 ,-1 , 0
  4434.3     .12       0  4524.1     .05       0  4614.8     .12       0
  4997.4     .07       0  5002.1     .12       0  5029.3     .05       0
Bank Sta=4997.4,5002.1
XS Rating Curve= 0 ,0
Exp/Cntr=0.3,0.1

Type RM Length L Ch R = 1 ,26227   ,718,718,718
BEGIN DESCRIPTION:
LOST HOLLOW CREEK 58.0
END DESCRIPTION:
XS GIS Cut Line= 3
      2807932.57     10190532.53      2807695.59     10190110.65
      2807000.52     10190058.59
#Sta/Elev= 30
  4369.3 1361.34  4373.8 1361.64  4498.1 1357.99  4586.6 1356.61  4660.1 1352.57
  4762.7 1349.06  4779.6 1347.63  4784.4  1346.8  4800.3 1346.19  4806.1 1345.24
    4822 1344.65  4827.8  1342.8  4848.9 1341.57  4923.3 1338.94  4933.9  1339.5
  4953.4 1338.62  4973.4 1336.56  4983.5 1333.63    4991 1330.63  4991.4 1330.13
  4995.6 1330.13  4995.9 1330.63  5024.8 1333.72  5033.6  1338.1  5043.6 1341.13
  5053.6 1342.98  5123.8 1343.51  5224.1 1345.83  5444.7 1353.34  5550.2 1358.38
#Mann= 5 ,-1 , 0
  4369.3     .05       0  4779.6     .12       0  4933.9     .05       0
    4991     .05       0  4995.9     .05       0
Bank Sta=4991,4995.9
XS Rating Curve= 0 ,0
Exp/Cntr=0.3,0.1

Type RM Length L Ch R = 1 ,25509   ,555,555,555
BEGIN DESCRIPTION:
LOST HOLLOW CREEK 56.0
END DESCRIPTION:
XS GIS Cut Line= 3
      2808385.67     10189558.57      2807961.22     10189498.67
       2807405.7     10189503.11
#Sta/Elev= 30
  4434.8 1358.76  4485.3  1355.7  4510.1 1354.97  4535.8 1352.97  4652.3 1346.36
  4717.6 1344.03  4747.9 1342.07  4863.5 1337.32    4869 1336.52    4949 1334.65
    4959 1333.57    4969 1333.39    4979 1330.81    4989 1326.53    4999 1325.13
  5006.4 1324.98  5006.8 1324.48  5011.2 1324.48  5011.6 1324.98    5019 1327.45
    5039 1331.28    5069  1332.7    5089 1335.01    5099 1334.71    5129 1336.87
    5179 1338.11    5219 1340.52    5269 1341.92    5359 1346.21    5419 1351.88
#Mann= 3 ,-1 , 0
  4434.8     .05       0  5006.4     .05       0  5011.6     .05       0
Bank Sta=5006.4,5011.6
XS Rating Curve= 0 ,0
Exp/Cntr=0.3,0.1

Type RM Length L Ch R = 1 ,24954   ,361,361,361
BEGIN DESCRIPTION:
LOST HOLLOW CREEK 55.0
END DESCRIPTION:
XS GIS Cut Line= 3
      2808255.69     10188853.11       2807823.2     10189055.96
       2807555.7      10189203.1
#Sta/Elev= 30
    4648 1408.92  4650.8 1408.92  4656.7 1406.28  4679.5 1399.43    4685 1399.27
  4692.2 1396.34  4707.8 1393.81  4714.3 1390.15  4730.6 1386.01  4736.4 1382.81
  4747.4  1379.8  4753.5 1377.25    4759 1377.51  4804.6 1367.69  4850.3 1353.42
  4867.6 1346.03  4886.1 1342.05  4895.9 1340.59  4902.1 1338.57  4924.2 1334.04
  4941.5 1332.82  4957.3  1330.6  4990.1 1320.41  4990.5 1319.91  4995.3 1320.41
  5023.6 1323.13  5045.6 1328.76  5061.2 1331.16  5351.1 1336.77    5431 1341.92
#Mann= 4 ,-1 , 0
    4648     .12       0  4886.1     .05       0  4990.1     .03       0
  4995.3     .05       0
Bank Sta=4990.1,4995.3
XS Rating Curve= 0 ,0
Exp/Cntr=0.3,0.1

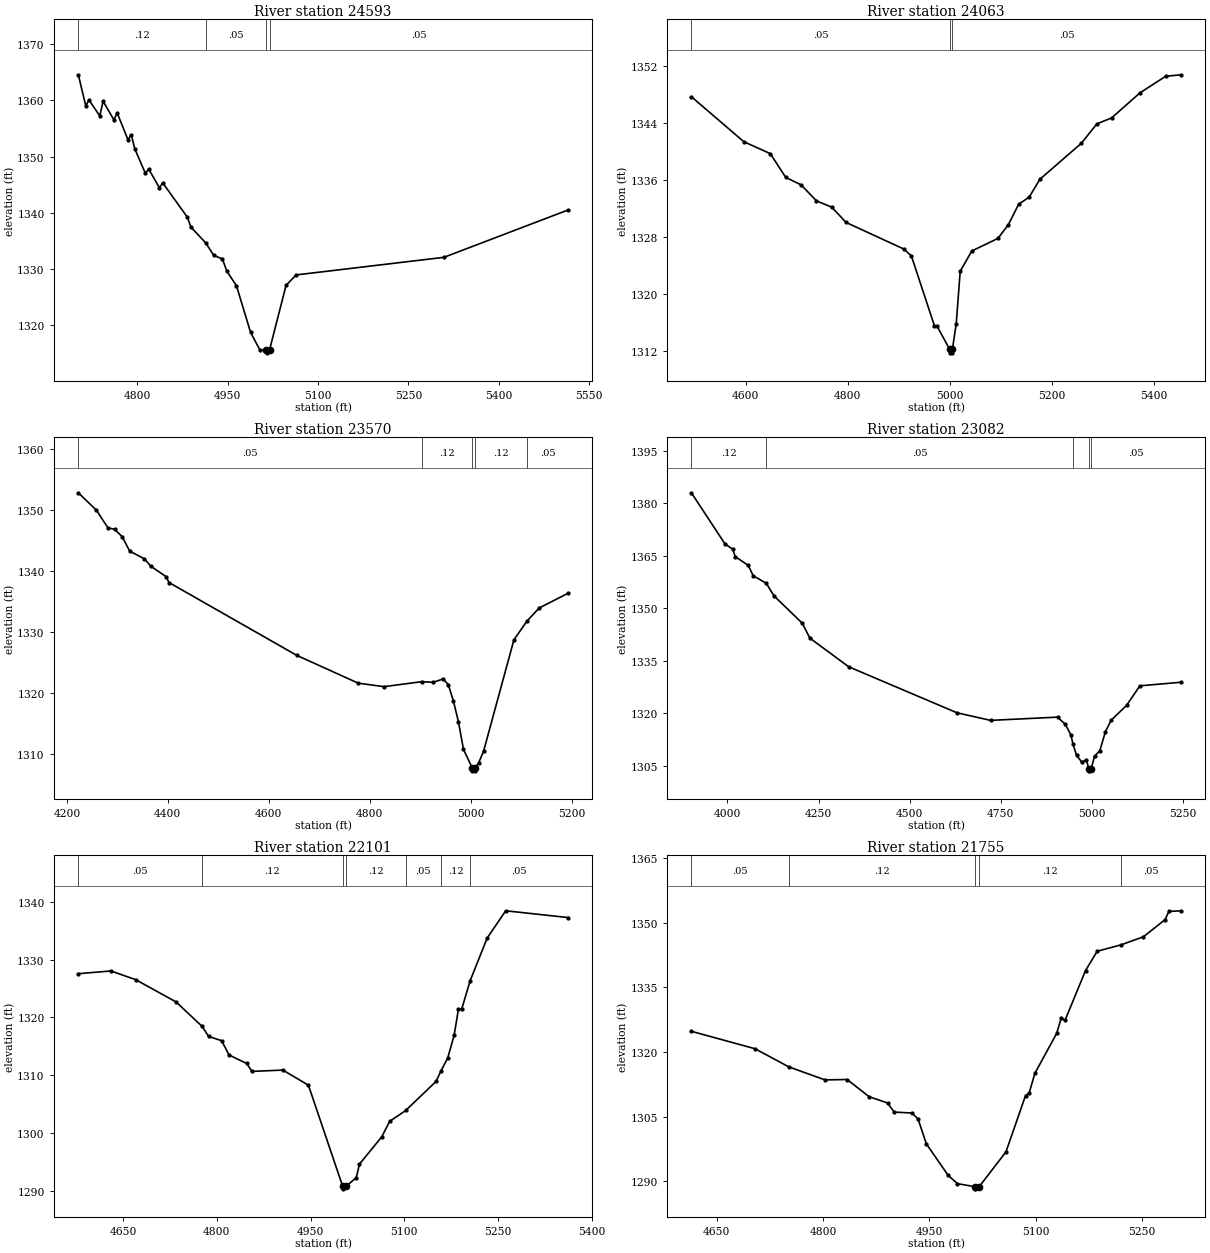
Type RM Length L Ch R = 1 ,24593   ,530,530,530
BEGIN DESCRIPTION:
LOST HOLLOW CREEK 54.0
END DESCRIPTION:
XS GIS Cut Line= 3
      2808091.39     10188542.96      2807711.46     10188709.49
       2807461.8     10189018.78
#Sta/Elev= 30
  4702.4 1364.55  4714.7 1359.03  4720.1 1360.06    4738 1357.22  4743.5 1359.84
  4761.4 1356.53  4766.9 1357.75  4784.8 1352.98  4790.2 1353.89    4796 1351.39
  4813.6 1347.01  4819.1 1347.78    4837 1344.42  4842.4 1345.31  4883.3  1339.2
  4889.2 1337.43  4913.9 1334.61    4927 1332.41  4941.4 1331.77  4948.8 1329.59
  4964.8 1326.99  4988.1 1318.72  5003.4 1315.61  5014.4 1315.55  5014.8 1315.05
  5019.6 1315.55  5047.1 1327.07  5063.7 1328.92  5308.9 1332.05  5514.7 1340.47
#Mann= 4 ,-1 , 0
  4702.4     .12       0  4913.9     .05       0  5014.4     .03       0
  5019.6     .05       0
Bank Sta=5014.4,5019.6
XS Rating Curve= 0 ,0
Exp/Cntr=0.3,0.1

Type RM Length L Ch R = 1 ,24063   ,493,493,493
BEGIN DESCRIPTION:
LOST HOLLOW CREEK 53.0
END DESCRIPTION:
XS GIS Cut Line= 3
      2808109.64     10188188.78      2807755.68     10188153.11
      2807164.31     10188274.72
#Sta/Elev= 30
  4493.8 1347.65  4596.7 1341.34  4648.5 1339.67  4678.7 1336.34  4708.8 1335.29
    4739 1333.05  4769.1 1332.15    4797 1330.02  4910.8 1326.27  4925.1  1325.3
  4970.3 1315.49  4975.4 1315.46    5000 1312.23  5000.4 1311.73  5004.9 1311.73
  5005.4 1312.23  5012.9 1315.81  5020.7 1323.18  5043.5 1326.02  5094.6 1327.78
    5115 1329.69  5135.4 1332.59  5155.8 1333.56  5176.8 1336.07  5257.9 1341.11
  5288.5 1343.84  5317.6 1344.69  5373.1  1348.2  5423.4 1350.52  5453.3 1350.73
#Mann= 3 ,-1 , 0
  4493.8     .05       0    5000     .05       0  5005.4     .05       0
Bank Sta=5000,5005.4
XS Rating Curve= 0 ,0
Exp/Cntr=0.3,0.1

Type RM Length L Ch R = 1 ,23570   ,488,488,488
BEGIN DESCRIPTION:
LOST HOLLOW CREEK 52.0
END DESCRIPTION:
XS GIS Cut Line= 3
      2808224.23     10188045.54      2807719.03      10187704.4
      2807358.84     10187706.99
#Sta/Elev= 30
  4222.8 1352.78  4258.6 1349.92  4281.4 1347.04  4294.6 1346.78  4309.6 1345.59
  4324.5 1343.21  4353.8 1341.94  4366.5 1340.72  4396.5 1339.03  4402.5 1338.05
  4655.4 1326.11  4777.1 1321.55  4828.1 1320.97  4903.5 1321.79  4925.7 1321.68
  4945.7 1322.24  4955.7 1321.29  4965.7 1318.64  4975.7 1315.25  4985.7 1310.69
    5003 1307.66  5003.4 1307.16    5008 1307.16  5008.4 1307.66  5015.7 1308.44
  5025.7 1310.42  5085.7 1328.66  5111.8 1331.75  5135.8 1333.88  5192.6 1336.28
#Mann= 5 ,-1 , 0
  4222.8     .05       0  4903.5     .12       0    5003     .07       0
  5008.4     .12       0  5111.8     .05       0
Bank Sta=5003,5008.4
XS Rating Curve= 0 ,0
Exp/Cntr=0.3,0.1

Type RM Length L Ch R = 1 ,23082   ,981,981,981
BEGIN DESCRIPTION:
LOST HOLLOW CREEK 51.0
END DESCRIPTION:
XS GIS Cut Line= 3
       2808455.7     10188103.13      2807786.74     10187371.07
      2807601.86     10187071.62
#Sta/Elev= 30
    3901    1383  3993.2 1368.39  4014.2 1366.88  4021.6 1364.72  4056.7 1362.27
  4070.9 1359.26  4106.5 1357.12  4127.7 1353.53  4205.4  1345.7  4226.3 1341.43
    4333 1333.23  4630.3 1320.08  4722.2 1317.92  4906.1 1318.85  4927.3 1316.78
  4942.7 1313.74  4948.5 1311.08  4958.1 1307.93  4972.5 1305.98  4985.3 1306.65
  4991.8 1303.99  4992.3 1303.49  4997.7 1303.99  5007.8 1307.69  5021.9 1309.23
  5037.3 1314.67  5052.7 1317.92  5095.3 1322.19  5131.9  1327.8  5244.6 1328.82
#Mann= 5 ,-1 , 0
    3901     .12       0  4106.5     .05       0  4948.5     .12       0
  4991.8     .03       0  4997.7     .05       0
Bank Sta=4991.8,4997.7
XS Rating Curve= 0 ,0
Exp/Cntr=0.3,0.1

Type RM Length L Ch R = 1 ,22101   ,346,346,346
BEGIN DESCRIPTION:
LOST HOLLOW CREEK 49.0
END DESCRIPTION:
XS GIS Cut Line= 3
      2808385.72     10186644.51      2808117.47     10186566.38
      2807629.32     10186691.01
#Sta/Elev= 30
  4578.5 1327.56  4630.6 1328.03    4670 1326.54  4734.8 1322.68  4776.6 1318.44
  4786.8 1316.72  4807.7 1315.97  4819.6  1313.5  4847.9 1312.03  4856.2 1310.66
  4905.7 1310.89  4946.6 1308.27  5001.2 1290.85  5001.7 1290.35  5007.3 1290.85
  5023.1 1292.27  5028.3 1294.63    5064 1299.36  5076.5 1302.01  5102.2  1303.9
  5150.9 1308.94  5158.6 1310.73  5169.4 1312.98  5179.7  1316.9  5186.6 1321.42
  5191.7 1321.39  5205.3 1326.34  5232.6 1333.73  5262.2 1338.44  5361.7 1337.27
#Mann= 7 ,-1 , 0
  4578.5     .05       0  4776.6     .12       0  5001.2     .07       0
  5007.3     .12       0  5102.2     .05       0  5158.6     .12       0
  5205.3     .05       0
Bank Sta=5001.2,5007.3
XS Rating Curve= 0 ,0
Exp/Cntr=0.3,0.1

Type RM Length L Ch R = 1 ,21755   ,396,396,396
BEGIN DESCRIPTION:
LOST HOLLOW CREEK 48.0
END DESCRIPTION:
XS GIS Cut Line= 3
      2808380.51      10186449.2      2808109.66     10186355.44
      2807713.82     10186274.71
#Sta/Elev= 30
  4614.1 1324.81  4703.9 1320.76  4751.6 1316.54  4802.6 1313.52  4833.8 1313.61
  4864.9 1309.61  4890.8 1308.16  4900.2 1306.04  4925.2 1305.83  4933.8 1304.46
  4945.6 1298.66  4976.2 1291.36  4989.5 1289.41    5014 1288.71  5014.5 1288.21
  5020.1 1288.71  5057.9 1296.81  5085.5 1309.89  5090.6 1310.49  5098.7 1315.06
  5129.3  1324.3    5136 1327.95  5141.1 1327.32  5170.1 1338.92  5186.5  1343.4
  5220.3  1344.9  5251.8 1346.77  5282.4 1350.76  5287.6 1352.65  5304.7 1352.81
#Mann= 5 ,-1 , 0
  4614.1     .05       0  4751.6     .12       0    5014     .07       0
  5020.1     .12       0  5220.3     .05       0
Bank Sta=5014,5020.1
XS Rating Curve= 0 ,0
Exp/Cntr=0.3,0.1

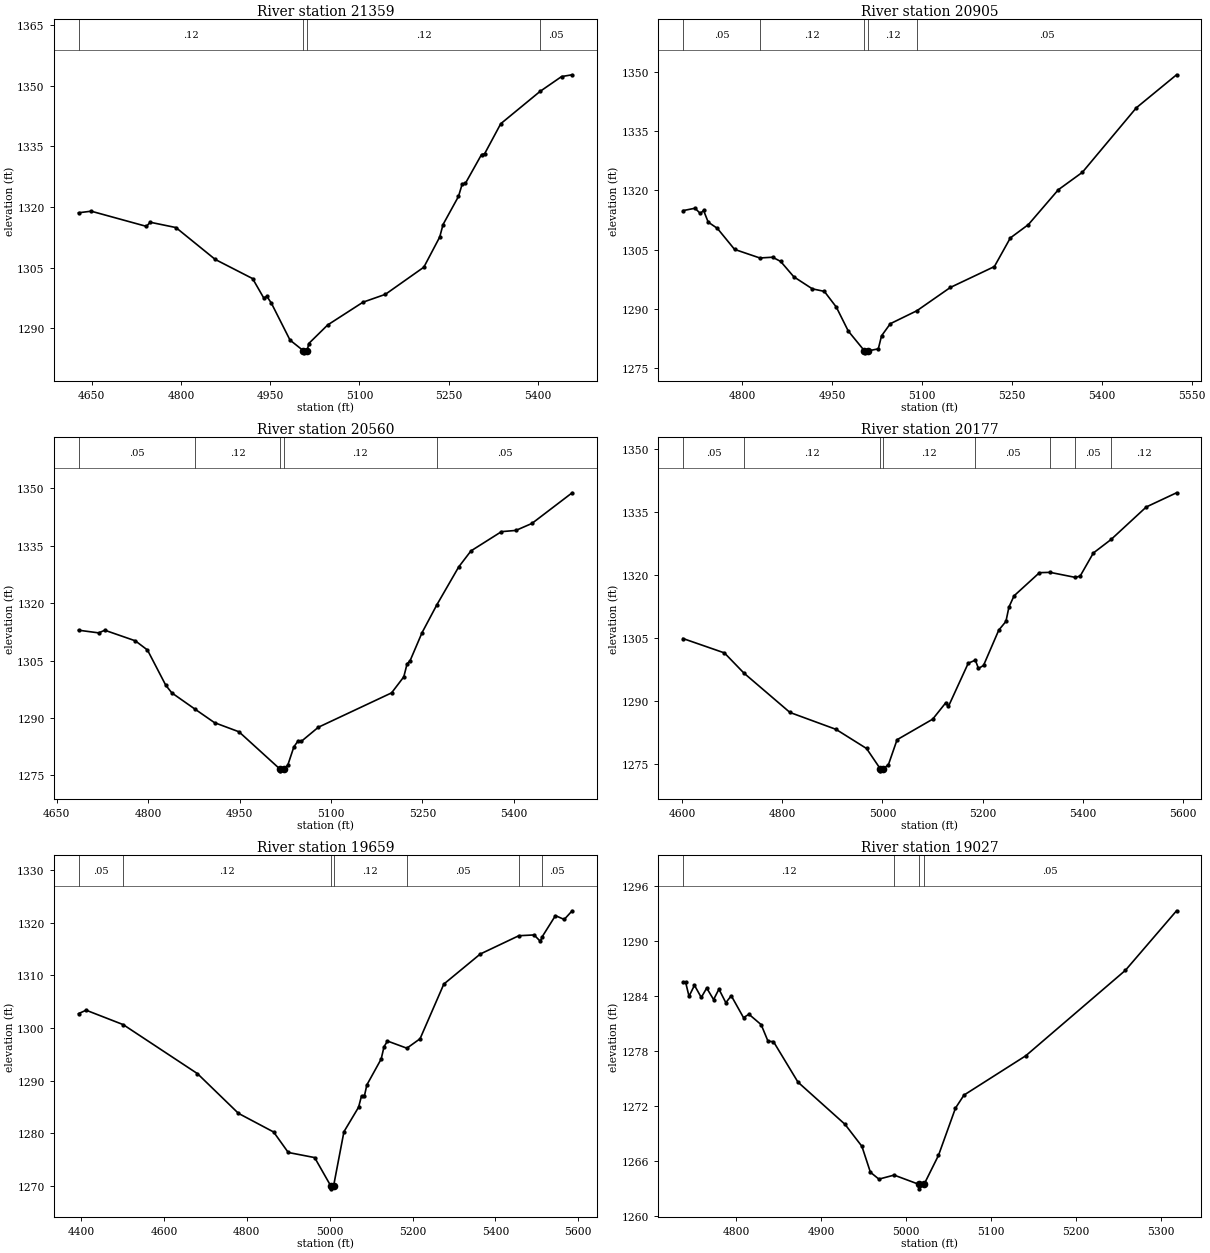
Type RM Length L Ch R = 1 ,21359   ,454,454,454
BEGIN DESCRIPTION:
LOST HOLLOW CREEK 47.0
END DESCRIPTION:
XS GIS Cut Line= 3
      2808518.48     10186170.52      2808357.05     10186040.34
      2807763.33     10185852.85
#Sta/Elev= 30
  4627.6 1318.59  4648.9 1318.98  4741.7 1315.23  4748.1 1316.25  4791.3 1314.94
  4857.4 1307.06  4920.3 1302.32    4939 1297.53  4944.3 1297.93  4951.8 1296.26
  4983.2 1287.12  5005.8 1284.47  5006.3 1283.97    5012 1284.47  5014.7 1286.27
  5046.5 1290.86  5105.9 1296.49  5143.5 1298.43  5208.2 1305.14  5234.9  1312.6
  5240.5 1315.69  5266.4 1322.62  5272.8 1325.75  5278.1 1325.87  5305.2 1332.98
  5310.4 1333.18  5337.5  1340.6  5403.6 1348.59  5439.8 1352.26  5457.6  1352.7
#Mann= 4 ,-1 , 0
  4627.6     .12       0  5005.8     .07       0    5012     .12       0
  5403.6     .05       0
Bank Sta=5005.8,5012
XS Rating Curve= 0 ,0
Exp/Cntr=0.3,0.1

Type RM Length L Ch R = 1 ,20905   ,345,345,345
BEGIN DESCRIPTION:
LOST HOLLOW CREEK 46.0
END DESCRIPTION:
XS GIS Cut Line= 3
      2808594.07      10185631.5      2808416.95     10185550.76
      2807788.72      10185584.5
#Sta/Elev= 30
    4701 1314.87  4721.2 1315.48    4730 1314.16  4735.5 1314.91  4743.2 1311.97
  4758.5 1310.39  4787.2 1305.08  4829.4 1302.91  4850.7  1303.1  4864.1 1302.04
  4886.1 1298.15    4917 1295.11    4937 1294.47    4957  1290.5    4977 1284.44
    5004 1279.44  5004.5 1278.94  5010.2 1279.44  5027.1 1279.95  5032.5 1283.24
  5047.1  1286.3  5091.5 1289.58  5147.3 1295.46  5220.8 1300.74  5247.4 1307.97
  5277.5 1311.34  5327.5 1320.15  5367.6 1324.55  5457.7 1340.86  5524.8  1349.2
#Mann= 5 ,-1 , 0
    4701     .05       0  4829.4     .12       0    5004     .07       0
  5010.2     .12       0  5091.5     .05       0
Bank Sta=5004,5010.2
XS Rating Curve= 0 ,0
Exp/Cntr=0.3,0.1

Type RM Length L Ch R = 1 ,20560   ,383,383,383
BEGIN DESCRIPTION:
LOST HOLLOW CREEK 45.0
END DESCRIPTION:
XS GIS Cut Line= 3
      2808588.81     10185209.61      2808347.12     10185211.27
      2807779.83     10185243.41
#Sta/Elev= 30
  4685.8 1312.93  4718.9 1312.23  4728.9 1312.92  4778.9 1310.16  4798.9 1307.75
  4828.9 1298.55  4838.9 1296.54  4877.3 1292.25  4908.9 1288.76    4949 1286.38
    5016 1276.67  5016.5 1276.17  5022.2 1276.67  5029.1 1277.65  5039.1 1282.44
  5046.2 1284.04  5051.3 1283.87  5079.2 1287.56  5199.4 1296.55  5219.4 1300.73
  5224.8  1304.1  5229.8 1304.97  5249.5 1312.32  5273.7 1319.57  5309.5 1329.46
  5329.6 1333.65  5379.7 1338.69  5403.3 1339.01  5429.7 1340.84  5495.7 1348.85
#Mann= 5 ,-1 , 0
  4685.8     .05       0  4877.3     .12       0    5016     .07       0
  5022.2     .12       0  5273.7     .05       0
Bank Sta=5016,5022.2
XS Rating Curve= 0 ,0
Exp/Cntr=0.3,0.1

Type RM Length L Ch R = 1 ,20177   ,518,518,518
BEGIN DESCRIPTION:
LOST HOLLOW CREEK 44.0
END DESCRIPTION:
XS GIS Cut Line= 3
       2808614.9      10184884.1      2808310.18     10184821.59
      2807646.16     10184936.17
#Sta/Elev= 30
  4601.8 1304.96  4684.6 1301.53  4723.5 1296.73  4815.4 1287.35  4907.2 1283.33
  4968.2 1278.77  4995.5 1273.95    4996 1273.45  5001.8 1273.95  5011.9 1274.94
  5029.1 1280.86  5100.1 1285.75  5126.6 1289.71  5131.6 1288.79  5171.1 1299.08
  5185.3  1299.8  5191.5 1297.82  5201.6 1298.55    5232 1306.96  5246.3 1309.03
  5252.3 1312.45  5262.5 1315.12  5313.2 1320.64  5334.5 1320.71  5384.8 1319.51
  5394.4 1319.83  5420.7 1325.32  5456.1 1328.54  5526.3 1336.28  5586.7 1339.66
#Mann= 8 ,-1 , 0
  4601.8     .05       0  4723.5     .12       0  4995.5     .07       0
  5001.8     .12       0  5185.3     .05       0  5334.5     .12       0
  5384.8     .05       0  5456.1     .12       0
Bank Sta=4995.5,5001.8
XS Rating Curve= 0 ,0
Exp/Cntr=0.3,0.1

Type RM Length L Ch R = 1 ,19659   ,632,632,632
BEGIN DESCRIPTION:
LOST HOLLOW CREEK 43.0
END DESCRIPTION:
XS GIS Cut Line= 3
      2808622.65     10184772.08      2808130.49     10184279.92
      2807713.87     10184548.12
#Sta/Elev= 30
  4393.9 1302.75  4412.2  1303.4  4501.7 1300.66  4680.9 1291.35  4779.9  1283.8
  4864.8 1280.26  4900.1 1276.37  4963.8  1275.4  5003.1 1269.96  5003.6 1269.46
  5009.4 1269.96  5034.5 1280.31  5069.8 1284.96  5076.9  1287.1    5084 1287.14
  5089.8  1289.2  5124.4 1294.13  5131.3 1296.47  5139.6 1297.54  5186.4 1296.18
  5218.2 1297.97  5275.6 1308.36  5363.5 1314.07  5456.6 1317.55  5493.5  1317.7
  5508.7 1316.47  5512.8 1317.33    5545 1321.37  5566.2 1320.64  5585.4 1322.29
#Mann= 7 ,-1 , 0
  4393.9     .05       0  4501.7     .12       0  5003.1     .07       0
  5009.4     .12       0  5186.4     .05       0  5456.6     .12       0
  5512.8     .05       0
Bank Sta=5003.1,5009.4
XS Rating Curve= 0 ,0
Exp/Cntr=0.3,0.1

Type RM Length L Ch R = 1 ,19027   ,263,263,263
BEGIN DESCRIPTION:
LOST HOLLOW CREEK 42.0
END DESCRIPTION:
XS GIS Cut Line= 3
      2808605.68     10184003.11      2808495.07     10183915.34
      2808055.64     10183903.11
#Sta/Elev= 30
  4737.5 1285.53  4740.7 1285.53  4744.7 1284.01  4751.1 1285.21  4759.1 1283.88
  4765.5 1284.91  4773.6 1283.65  4779.9 1284.79    4788 1283.31  4794.4 1284.07
  4808.8 1281.68  4815.2 1282.05  4829.6 1280.91  4837.7 1279.09    4844 1279.07
  4872.9 1274.64  4928.1 1270.05  4948.1 1267.64  4958.1 1264.81  4968.1 1264.06
    4986  1264.5  5014.9  1263.5  5015.4    1263  5021.3  1263.5  5038.2 1266.65
  5058.2 1271.81  5068.2 1273.23  5140.9 1277.52  5258.2 1286.85  5318.3 1293.34
#Mann= 4 ,-1 , 0
  4737.5     .12       0    4986     .05       0  5014.9     .05       0
  5021.3     .05       0
Bank Sta=5014.9,5021.3
XS Rating Curve= 0 ,0
Exp/Cntr=0.3,0.1

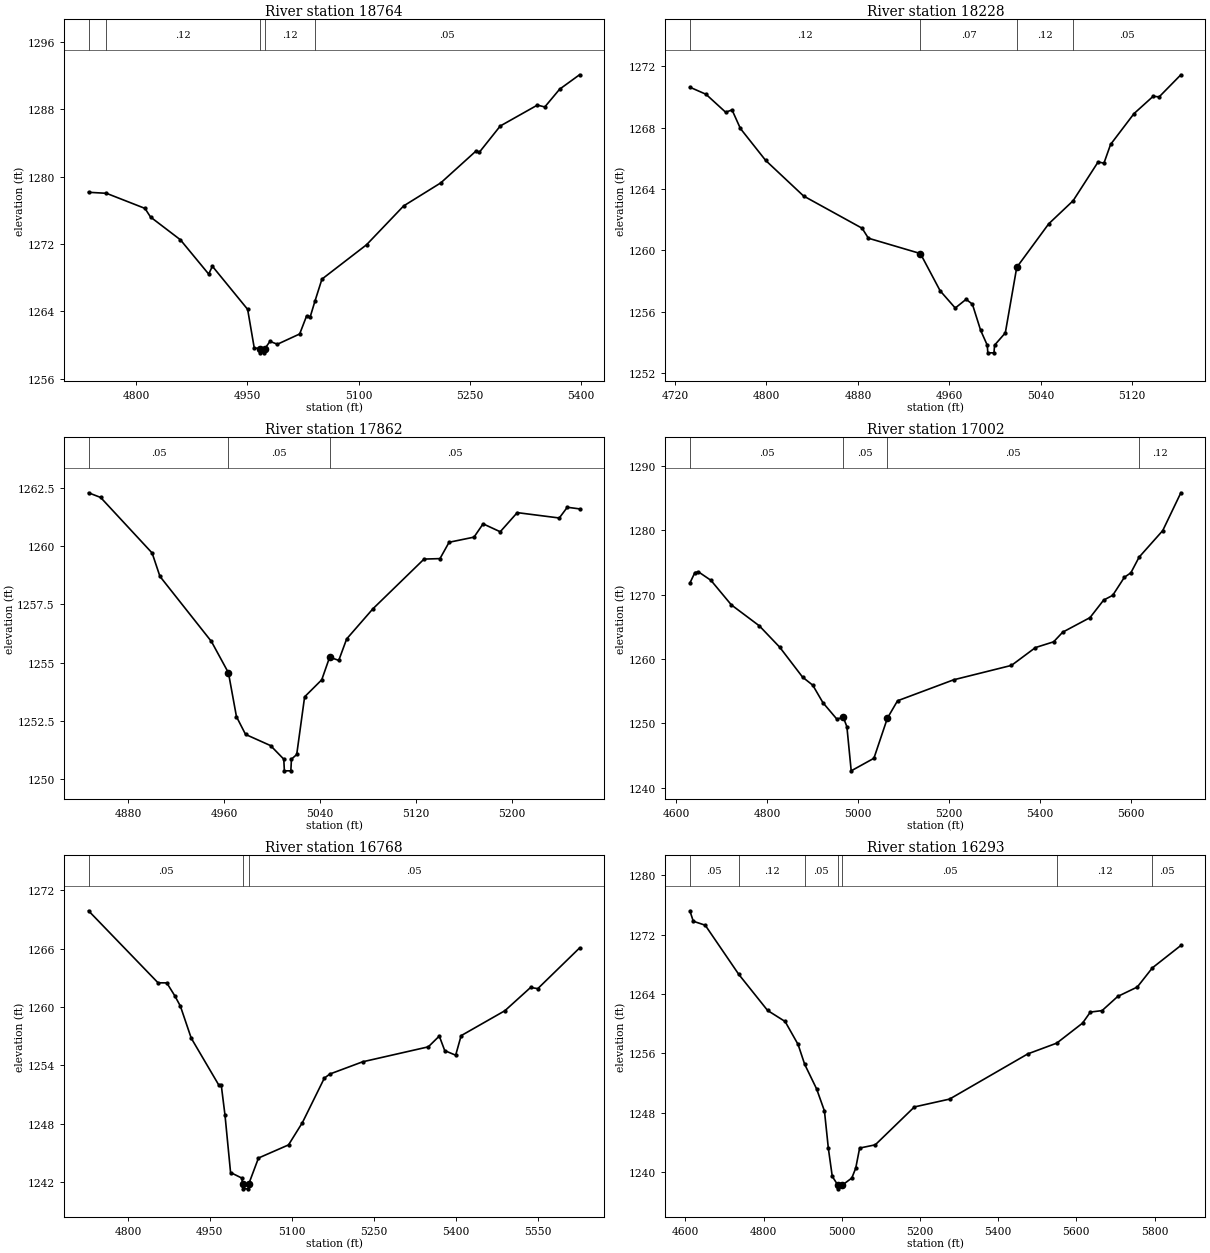
Type RM Length L Ch R = 1 ,18764   ,536,536,536
BEGIN DESCRIPTION:
LOST HOLLOW CREEK 41.0
END DESCRIPTION:
XS GIS Cut Line= 3
      2808648.75     10183686.18      2808422.81     10183661.25
      2807988.95     10183641.98
#Sta/Elev= 30
  4736.1 1278.14  4760.2 1278.02  4812.1 1276.23  4819.7  1275.2  4859.9  1272.5
    4898 1268.43    4903 1269.36  4950.5 1264.24  4959.4 1259.66  4967.3 1259.58
  4967.8 1259.08  4973.2 1259.08  4973.7 1259.58  4980.6 1260.44  4990.6  1260.1
  5020.6 1261.32  5029.9 1263.45  5034.9 1263.38  5041.1 1265.19  5050.6 1267.83
  5110.7 1271.91  5160.7 1276.52  5210.8 1279.26  5257.6 1282.99  5262.7 1282.89
  5290.9 1286.01  5340.9 1288.49  5350.9 1288.27  5370.9 1290.38  5397.7 1292.09
#Mann= 5 ,-1 , 0
  4736.1     .05       0  4760.2     .12       0  4967.3     .07       0
  4973.7     .12       0  5041.1     .05       0
Bank Sta=4967.3,4973.7
XS Rating Curve= 0 ,0
Exp/Cntr=0.3,0.1

Type RM Length L Ch R = 1 ,18228   ,366,366,366
BEGIN DESCRIPTION:
LOST HOLLOW CREEK 40.0
END DESCRIPTION:
XS GIS Cut Line= 3
      2808705.65     10183253.09      2808464.25       10183139.
      2808305.66     10183103.11
#Sta/Elev= 30
    4733 1270.63  4747.1 1270.17  4764.3    1269  4769.9 1269.15  4777.2 1267.94
  4799.3 1265.86  4832.5 1263.54  4883.7 1261.44  4889.2 1260.79  4934.7 1259.79
    4952 1257.36  4965.2 1256.24  4974.7 1256.81  4980.2 1256.49  4987.4 1254.79
  4993.2 1253.82  4993.7 1253.32  4999.1 1253.32  4999.6 1253.82    5009 1254.62
    5019 1258.89    5047 1261.73  5068.3 1263.23  5090.2 1265.76  5095.3 1265.68
  5101.1  1266.9  5121.6 1268.91  5138.4 1270.04  5143.6    1270  5162.6 1271.44
#Mann= 4 ,-1 , 0
    4733     .12       0  4934.7     .07       0    5019     .12       0
  5068.3     .05       0
Bank Sta=4934.7,5019
XS Rating Curve= 0 ,0
Exp/Cntr=0.3,0.1

Type RM Length L Ch R = 1 ,17862   ,860,860,860
BEGIN DESCRIPTION:
LOST HOLLOW CREEK 39.0
END DESCRIPTION:
XS GIS Cut Line= 3
      2808826.67     10183006.48      2808771.12     10182939.65
      2808528.04     10182726.96
#Sta/Elev= 30
  4846.7 1262.28  4856.8 1262.08  4899.8  1259.7  4906.3  1258.7  4949.3 1255.91
  4963.5 1254.57  4970.2 1252.69  4977.8 1251.93  4998.7 1251.45  5009.7 1250.87
  5010.2 1250.37  5015.6 1250.37  5016.1 1250.87  5020.5 1251.07  5027.1 1253.54
  5041.4 1254.27    5048 1255.24  5055.6  1255.1  5062.2 1256.02  5084.1 1257.31
  5126.8 1259.44  5140.1 1259.46  5147.7 1260.16  5168.5 1260.38  5176.1 1260.95
  5190.4 1260.61  5204.6 1261.43  5239.7  1261.2  5246.4 1261.66  5256.6 1261.59
#Mann= 3 , 0 , 0
  4846.7     .05       0  4963.5     .05       0    5048     .05       0
Bank Sta=4963.5,5048
XS Rating Curve= 0 ,0
Exp/Cntr=0.3,0.1

Type RM Length L Ch R = 1 ,17002   ,234,234,234
BEGIN DESCRIPTION:
LOST HOLLOW CREEK 38.0
END DESCRIPTION:
XS GIS Cut Line= 3
      2809285.55     10182397.09      2808845.48     10182179.23
      2808255.71     10182203.11
#Sta/Elev= 30
  4629.6 1271.79  4640.6 1273.42    4648 1273.56    4676 1272.22  4720.9 1268.41
  4782.6 1265.15  4827.4 1261.84  4877.9 1257.18  4900.3 1255.93  4922.7 1253.21
    4953 1250.69  4967.6 1250.92  4975.4 1249.48  4984.9 1242.63  5034.9 1244.58
  5064.6 1250.81  5086.9 1253.51  5210.5 1256.77  5337.9 1259.01  5390.7 1261.78
  5430.7 1262.67  5450.7 1264.17  5510.8 1266.43  5540.8 1269.15  5560.8 1269.89
  5586.6  1272.7  5600.8 1273.39  5618.9 1275.82  5670.9 1279.94  5710.9 1285.82
#Mann= 4 ,-1 , 0
  4629.6     .05       0  4967.6     .05       0  5064.6     .05       0
  5618.9     .12       0
Bank Sta=4967.6,5064.6
XS Rating Curve= 0 ,0
Exp/Cntr=0.3,0.1

Type RM Length L Ch R = 1 ,16768   ,475,475,475
BEGIN DESCRIPTION:
LOST HOLLOW CREEK 37.0
END DESCRIPTION:
XS GIS Cut Line= 3
      2809320.28     10182077.66      2809001.73     10182010.83
      2808429.42      10181972.2
#Sta/Elev= 30
  4727.8  1269.9  4855.1 1262.49  4871.1 1262.48  4885.8 1261.15    4896 1260.09
  4915.9 1256.79  4965.8 1252.02  4970.9 1251.94  4977.7 1248.87  4987.9 1242.97
  5008.4  1242.4    5010 1241.79  5010.5 1241.29  5020.7 1241.29  5021.2 1241.79
    5039 1244.46    5094 1245.81  5119.5 1248.11  5159.6 1252.68  5169.6  1253.1
  5229.7 1254.36    5350  1255.9  5370.1 1257.01  5380.1 1255.51  5400.1 1255.04
  5410.1 1257.05  5490.3 1259.62  5537.3 1262.01  5550.5 1261.89  5626.9 1266.07
#Mann= 3 ,-1 , 0
  4727.8     .05       0    5010     .05       0  5021.2     .05       0
Bank Sta=5010,5021.2
XS Rating Curve= 0 ,0
Exp/Cntr=0.3,0.1

Type RM Length L Ch R = 1 ,16293   ,456,456,456
BEGIN DESCRIPTION:
LOST HOLLOW CREEK 36.0
END DESCRIPTION:
XS GIS Cut Line= 3
      2809474.19     10181608.61      2809205.68     10181553.11
      2808224.23     10181570.63
#Sta/Elev= 30
  4611.5 1275.23  4620.2 1273.82  4650.8 1273.28  4736.7 1266.64  4810.3 1261.78
  4855.1 1260.29  4888.2  1257.2  4905.1 1254.52  4935.7 1251.19  4955.7 1248.22
  4965.7 1243.17  4975.7 1239.39  4990.1 1238.21  4990.6 1237.71  5001.4 1238.21
  5025.7 1239.17  5035.7  1240.5  5045.7 1243.21  5085.7 1243.65  5185.7 1248.76
  5275.7 1249.82  5475.8 1255.92  5549.8 1257.37  5615.8 1260.07  5635.8 1261.56
  5665.8 1261.76  5705.8 1263.67  5755.8 1264.94  5794.5 1267.53  5867.3 1270.55
#Mann= 7 ,-1 , 0
  4611.5     .05       0  4736.7     .12       0  4905.1     .05       0
  4990.1     .03       0  5001.4     .05       0  5549.8     .12       0
  5794.5     .05       0
Bank Sta=4990.1,5001.4
XS Rating Curve= 0 ,0
Exp/Cntr=0.3,0.1