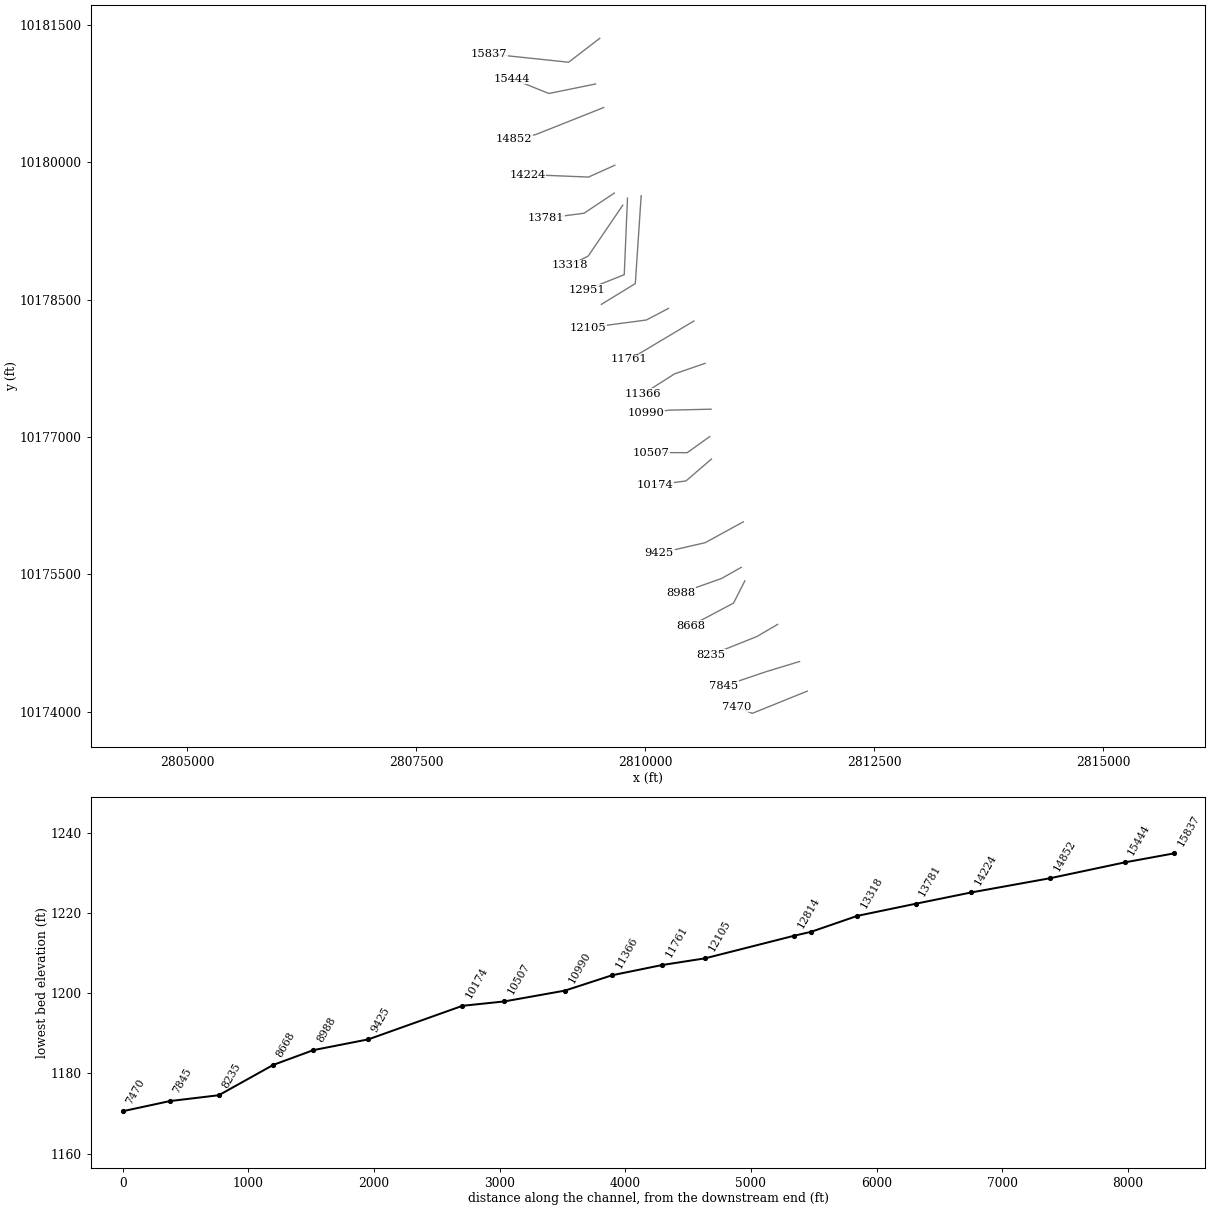
HEC-RAS study LOST HOLLOW CREEK.prj: LOST HOLLOW CREEK Base Level Engineering

--- LOST HOLLOW CREEK.g01 (geometry) --- (continued)

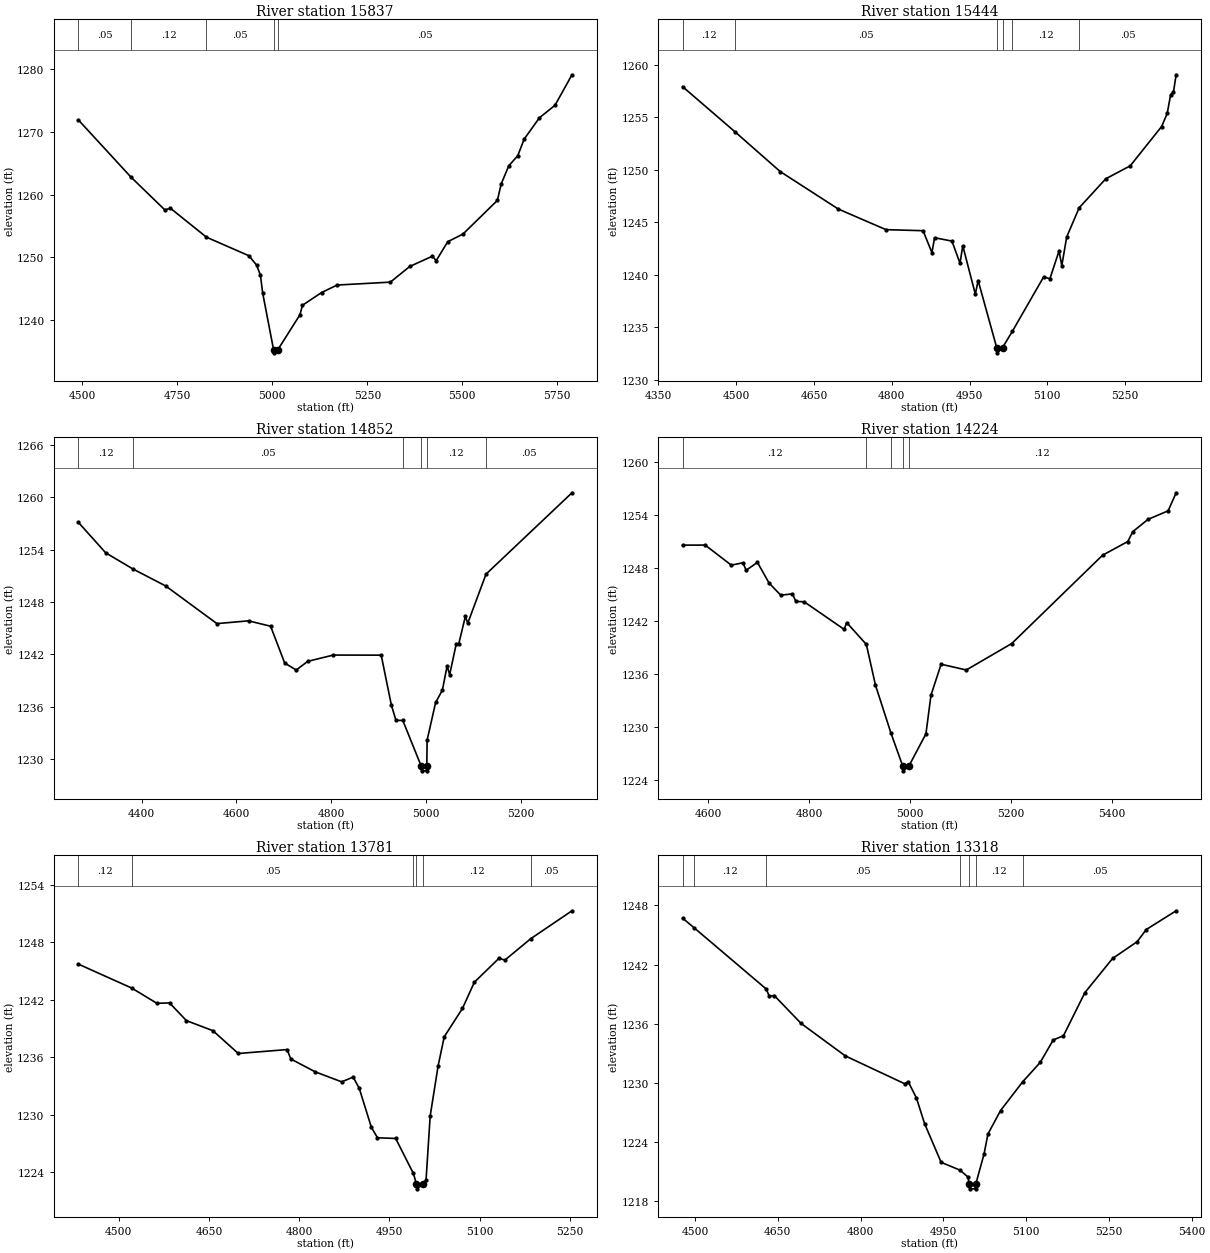
Type RM Length L Ch R = 1 ,15837   ,393,393,393
BEGIN DESCRIPTION:
LOST HOLLOW CREEK 35.0
END DESCRIPTION:
XS GIS Cut Line= 3
      2809505.66      10181353.1      2809166.02     10181092.12
      2808300.43     10181183.23
#Sta/Elev= 30
  4489.8 1271.89  4628.1 1262.79  4717.2 1257.57  4731.7 1257.84  4826.8 1253.22
  4938.6 1250.26  4958.7 1248.77  4968.7 1247.17  4974.6 1244.35  5003.3  1235.3
  5003.8  1234.8  5014.6  1235.3  5072.6 1240.85  5079.4 1242.38  5129.6  1244.4
  5170.6  1245.6  5310.6 1246.06  5361.7 1248.56  5421.2 1250.19  5431.3 1249.48
  5461.5  1252.5  5501.7 1253.72  5592.2 1259.08  5602.2 1261.69  5622.3  1264.6
  5645.8 1266.19  5662.6 1268.83  5702.8 1272.24  5743.8 1274.23  5788.5 1279.09
#Mann= 5 ,-1 , 0
  4489.8     .05       0  4628.1     .12       0  4826.8     .05       0
  5003.3     .03       0  5014.6     .05       0
Bank Sta=5003.3,5014.6
XS Rating Curve= 0 ,0
Exp/Cntr=0.3,0.1

Type RM Length L Ch R = 1 ,15444   ,592,592,592
BEGIN DESCRIPTION:
LOST HOLLOW CREEK 34.0
END DESCRIPTION:
XS GIS Cut Line= 3
      2809460.11      10180854.5      2808951.07     10180750.76
      2808549.69     10180911.57
#Sta/Elev= 30
  4396.6 1257.92  4498.5 1253.58  4584.8 1249.83  4697.1 1246.25  4788.9 1244.29
  4860.4 1244.19  4877.5  1242.1  4882.6 1243.52  4916.1  1243.2  4931.6 1241.09
    4937 1242.75  4961.2 1238.14  4966.6 1239.44  5002.4 1233.05  5002.9 1232.55
  5013.7 1233.05  5032.8 1234.62    5093 1239.79    5105 1239.61  5122.6 1242.25
    5128 1240.87  5137.4 1243.59  5161.4 1246.37  5212.8 1249.14  5259.9 1250.37
  5320.5 1254.12  5331.3 1255.37  5337.9 1257.17  5343.3 1257.41  5348.5 1259.05
#Mann= 6 ,-1 , 0
  4396.6     .12       0  4498.5     .05       0  5002.4     .03       0
  5013.7     .05       0  5032.8     .12       0  5161.4     .05       0
Bank Sta=5002.4,5013.7
XS Rating Curve= 0 ,0
Exp/Cntr=0.3,0.1

Type RM Length L Ch R = 1 ,14852   ,628,628,628
BEGIN DESCRIPTION:
LOST HOLLOW CREEK 33.0
END DESCRIPTION:
XS GIS Cut Line= 3
      2809549.09     10180597.34       2808806.4     10180301.81
      2808569.95     10180251.34
#Sta/Elev= 30
  4266.8 1257.14  4324.3 1253.65  4381.9 1251.79    4451 1249.84    4559 1245.52
  4625.6 1245.84  4672.2 1245.22  4701.9    1241  4726.2 1240.19  4750.5 1241.19
  4804.4 1241.91  4905.5  1241.9    4927 1236.15  4936.6 1234.42  4951.1  1234.4
  4990.2 1229.12  4990.7 1228.62  5001.2 1228.62  5001.7 1229.12  5002.3 1232.13
  5020.3 1236.47  5034.6 1237.89  5044.5 1240.65  5049.9 1239.66  5063.8  1243.2
  5069.1  1243.2    5083 1246.34  5088.1 1245.57  5126.6  1251.2  5307.9 1260.54
#Mann= 6 ,-1 , 0
  4266.8     .12       0  4381.9     .05       0  4951.1     .12       0
  4990.2     .07       0  5001.7     .12       0  5126.6     .05       0
Bank Sta=4990.2,5001.7
XS Rating Curve= 0 ,0
Exp/Cntr=0.3,0.1

Type RM Length L Ch R = 1 ,14224   ,443,443,443
BEGIN DESCRIPTION:
LOST HOLLOW CREEK 32.0
END DESCRIPTION:
XS GIS Cut Line= 3
      2809670.61     10179966.91      2809383.04     10179837.78
      2808719.82     10179864.87
#Sta/Elev= 30
  4548.7 1250.58  4593.5 1250.59  4645.3 1248.32  4668.5 1248.59  4674.7 1247.74
  4697.2 1248.63  4720.3 1246.29  4743.5 1244.92  4766.7 1245.08  4773.3 1244.22
  4789.8 1244.18  4869.2 1241.06  4874.2 1241.83  4913.2 1239.36  4931.3 1234.76
  4961.7 1229.39  4985.6 1225.57  4986.1 1225.07  4997.2 1225.57  5031.4 1229.25
  5041.4 1233.62  5061.5 1237.12  5111.5 1236.47  5201.6 1239.46  5381.7 1249.44
  5431.8 1250.99  5441.8 1252.11  5471.8 1253.49  5511.8 1254.46  5527.7  1256.5
#Mann= 5 ,-1 , 0
  4548.7     .12       0  4913.2     .05       0  4961.7     .12       0
  4985.6     .07       0  4997.2     .12       0
Bank Sta=4985.6,4997.2
XS Rating Curve= 0 ,0
Exp/Cntr=0.3,0.1

Type RM Length L Ch R = 1 ,13781   ,463,463,463
BEGIN DESCRIPTION:
LOST HOLLOW CREEK 31.0
END DESCRIPTION:
XS GIS Cut Line= 3
      2809665.11     10179663.06      2809334.21     10179442.81
      2808915.35     10179387.47
#Sta/Elev= 30
  4433.2 1245.71  4521.8 1243.21  4563.6 1241.62  4584.6 1241.66  4612.7 1239.81
  4656.7 1238.76  4698.8 1236.38    4780 1236.79    4786 1235.81  4826.8 1234.46
  4870.6 1233.42  4889.7 1233.92  4899.8 1232.74    4920 1228.66  4930.1 1227.58
  4960.3 1227.51  4989.7 1223.86  4994.8 1222.75  4995.3 1222.25  5006.5 1222.75
  5010.8  1223.2  5017.6 1229.85  5030.9 1235.12    5041 1238.13  5071.3 1241.09
    5091 1243.82  5131.8 1246.31  5141.9 1246.14  5184.6 1248.36  5253.2 1251.28
#Mann= 6 ,-1 , 0
  4433.2     .12       0  4521.8     .05       0  4989.7     .12       0
  4994.8     .07       0  5006.5     .12       0  5184.6     .05       0
Bank Sta=4994.8,5006.5
XS Rating Curve= 0 ,0
Exp/Cntr=0.3,0.1

Type RM Length L Ch R = 1 ,13318   ,367,367,367
BEGIN DESCRIPTION:
LOST HOLLOW CREEK 30.0
END DESCRIPTION:
XS GIS Cut Line= 3
      2809757.37     10179530.68      2809379.78     10178975.15
      2809181.25     10178874.25
#Sta/Elev= 30
  4477.4 1246.71  4498.6 1245.72    4629 1239.52  4634.6 1238.78  4643.5 1238.86
  4692.1 1236.03  4772.3 1232.73  4880.1  1229.9  4886.1 1230.13  4901.1 1228.47
    4916 1225.85  4945.9 1221.93    4980 1221.14  4994.4 1220.45  4996.9 1219.74
  4997.4 1219.24  5008.3 1219.24  5008.8 1219.74  5023.8  1222.8  5030.7  1224.8
  5053.7 1227.19  5093.8 1230.11  5125.5 1232.07  5149.1 1234.35  5167.6 1234.78
  5206.5 1239.16  5256.6 1242.62  5301.1 1244.32  5317.7 1245.56  5371.8 1247.46
#Mann= 7 ,-1 , 0
  4477.4     .05       0  4498.6     .12       0    4629     .05       0
    4980     .12       0  4996.9     .07       0  5008.8     .12       0
  5093.8     .05       0
Bank Sta=4996.9,5008.8
XS Rating Curve= 0 ,0
Exp/Cntr=0.3,0.1

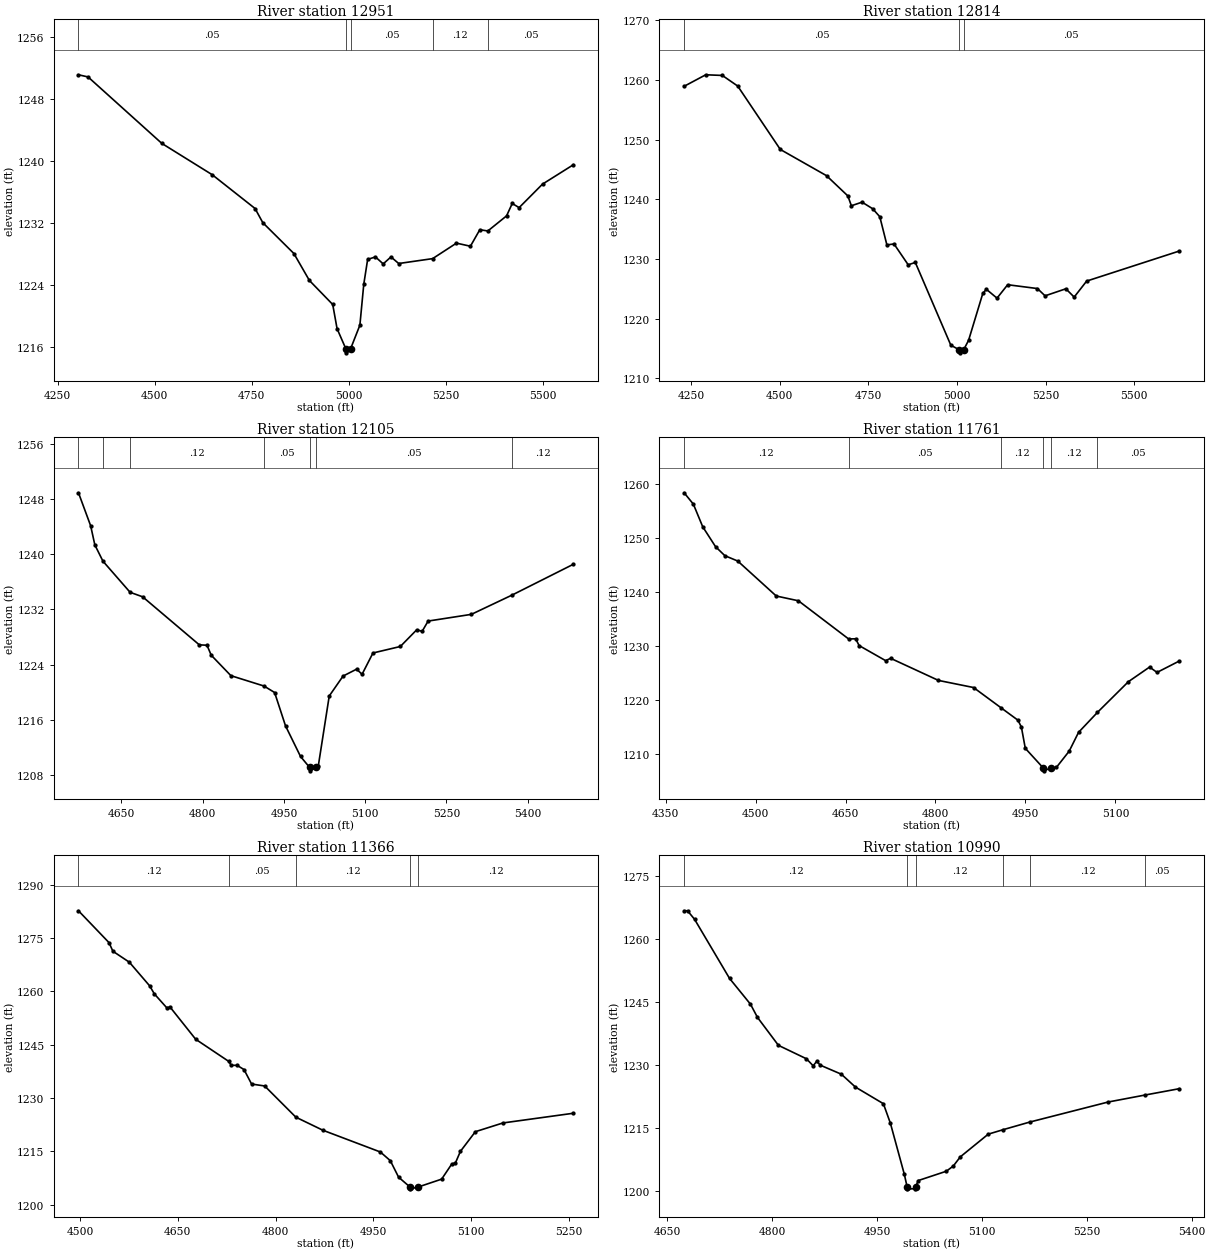
Type RM Length L Ch R = 1 ,12951   ,137,137,137
BEGIN DESCRIPTION:
LOST HOLLOW CREEK 29.0
END DESCRIPTION:
XS GIS Cut Line= 3
      2809808.53     10179607.79      2809773.37     10178771.81
       2809365.8     10178609.04
#Sta/Elev= 30
  4303.6 1251.17  4328.3 1250.89  4518.5 1242.31  4648.6 1238.26  4758.7 1233.91
  4778.7 1232.08  4858.8  1228.1  4898.8 1224.62  4958.9 1221.52  4970.1  1218.4
  4992.9 1215.78  4993.4 1215.28  5004.8 1215.78  5028.9 1218.85  5038.9 1224.12
  5048.9 1227.34    5069 1227.66    5089 1226.76    5109 1227.66    5129 1226.81
  5216.4 1227.44  5277.8 1229.44  5313.8 1229.04    5338 1231.17  5358.7 1231.01
    5407 1232.96  5421.6 1234.56  5439.3 1234.02  5499.7 1237.06  5579.2 1239.56
#Mann= 5 ,-1 , 0
  4303.6     .05       0  4992.9     .03       0  5004.8     .05       0
  5216.4     .12       0  5358.7     .05       0
Bank Sta=4992.9,5004.8
XS Rating Curve= 0 ,0
Exp/Cntr=0.3,0.1

Type RM Length L Ch R = 1 ,12814   ,709,709,709
BEGIN DESCRIPTION:
LOST HOLLOW CREEK 28.0
END DESCRIPTION:
XS GIS Cut Line= 3
      2809957.97     10179633.96      2809893.95     10178674.36
      2809523.42      10178447.1
#Sta/Elev= 30
  4230.1 1258.93  4291.1 1260.86  4337.9 1260.75  4381.3 1258.97  4501.5 1248.35
  4631.8 1243.96    4692 1240.57    4702 1238.92  4732.1 1239.52  4762.1 1238.42
  4782.2 1237.08  4802.2 1232.36  4822.3 1232.52  4862.3 1229.03  4882.4 1229.42
  4982.6 1215.56  5006.7 1214.78  5007.2 1214.28  5018.7 1214.78  5032.7 1216.38
  5072.8 1224.23  5082.8 1224.93  5112.9 1223.44    5143 1225.69  5226.9 1225.05
  5248.5 1223.83  5307.1 1225.01  5330.6 1223.62  5365.8  1226.3  5626.5 1231.32
#Mann= 3 ,-1 , 0
  4230.1     .05       0  5006.7     .05       0  5018.7     .05       0
Bank Sta=5006.7,5018.7
XS Rating Curve= 0 ,0
Exp/Cntr=0.3,0.1

Type RM Length L Ch R = 1 ,12105   ,344,344,344
BEGIN DESCRIPTION:
LOST HOLLOW CREEK 27.0
END DESCRIPTION:
XS GIS Cut Line= 3
      2810255.64     10178403.09      2810014.52     10178276.44
      2809379.01     10178192.43
#Sta/Elev= 30
  4570.8 1248.88  4593.3  1244.1    4601 1241.34    4616 1238.98  4666.1 1234.48
  4689.2 1233.83  4793.8 1226.88    4808 1226.82  4815.8 1225.38  4852.1 1222.42
  4913.2 1220.92  4932.8 1219.98  4952.9 1215.16  4980.6 1210.73  4997.3 1209.15
  4997.8 1208.65  5009.4 1209.15  5013.5  1209.4  5033.6 1219.48  5059.1 1222.36
  5084.1 1223.36  5094.2 1222.62  5114.3  1225.7  5164.8 1226.64    5195 1229.05
  5205.1 1228.84  5216.1 1230.32  5295.9 1231.29    5371 1234.08  5484.2 1238.54
#Mann= 7 ,-1 , 0
  4570.8     .12       0    4616     .05       0  4666.1     .12       0
  4913.2     .05       0  4997.3     .03       0  5009.4     .05       0
    5371     .12       0
Bank Sta=4997.3,5009.4
XS Rating Curve= 0 ,0
Exp/Cntr=0.3,0.1

Type RM Length L Ch R = 1 ,11761   ,395,395,395
BEGIN DESCRIPTION:
LOST HOLLOW CREEK 26.0
END DESCRIPTION:
XS GIS Cut Line= 3
      2810533.97       10178266.      2809898.11     10177886.22
      2809823.09     10177847.63
#Sta/Elev= 30
    4381 1258.33  4396.4 1256.23    4412 1252.05  4433.4 1248.37  4448.9 1246.71
  4470.4 1245.72  4534.6 1239.26  4571.5 1238.38  4655.2 1231.33  4666.9 1231.36
  4672.7 1230.11  4716.8 1227.33  4725.3 1227.75    4805 1223.67  4863.4 1222.36
  4909.1 1218.63  4937.4 1216.33  4943.2 1215.06  4949.7 1211.13  4979.9 1207.47
  4980.4 1206.97    4992 1207.47  5001.5  1207.6  5022.9 1210.61  5038.5 1214.08
    5070 1217.77  5121.6 1223.44  5156.9 1226.14  5169.3 1225.15    5206 1227.23
#Mann= 6 ,-1 , 0
    4381     .12       0  4655.2     .05       0  4909.1     .12       0
  4979.9     .07       0    4992     .12       0    5070     .05       0
Bank Sta=4979.9,4992
XS Rating Curve= 0 ,0
Exp/Cntr=0.3,0.1

Type RM Length L Ch R = 1 ,11366   ,376,376,376
BEGIN DESCRIPTION:
LOST HOLLOW CREEK 25.0
END DESCRIPTION:
XS GIS Cut Line= 3
      2810655.64      10177803.1      2810323.46     10177688.73
       2809979.5     10177470.25
#Sta/Elev= 30
  4497.7 1282.68  4544.5 1273.72  4550.5 1271.29  4575.7 1268.21  4606.9 1261.54
    4614  1259.3  4632.9 1255.42  4638.2 1255.57  4677.4 1246.53  4728.1  1240.3
  4731.8  1239.2  4740.9 1239.19  4751.5    1238  4763.1 1233.93  4783.2 1233.38
    4831  1224.6  4872.4 1220.93  4960.5 1214.81  4975.8 1212.37  4988.5 1207.72
  5006.1 1204.94  5006.6 1204.44  5018.3 1204.94  5054.5 1207.17  5069.8 1211.36
  5075.7 1211.76  5083.3 1214.99  5106.2 1220.52  5148.5 1222.98  5256.5 1225.71
#Mann= 5 ,-1 , 0
  4497.7     .12       0  4728.1     .05       0    4831     .12       0
  5006.1     .07       0  5018.3     .12       0
Bank Sta=5006.1,5018.3
XS Rating Curve= 0 ,0
Exp/Cntr=0.3,0.1

Type RM Length L Ch R = 1 ,10990   ,483,483,483
BEGIN DESCRIPTION:
LOST HOLLOW CREEK 24.0
END DESCRIPTION:
XS GIS Cut Line= 3
      2810720.57     10177302.45      2810262.15     10177291.94
      2810015.27     10177256.87
#Sta/Elev= 30
    4674 1266.81  4678.9 1266.81  4688.9 1264.79  4738.9 1250.72  4768.9 1244.57
  4778.9 1241.43  4808.9 1234.77  4848.9 1231.58  4858.6  1229.9  4863.6 1230.97
  4868.9 1230.04  4898.9  1227.9    4919 1224.84    4959 1220.88    4969 1216.25
    4989 1204.05  4992.9 1201.11  4993.4 1200.61  5004.6 1200.61  5005.1 1201.11
    5009 1202.59    5049  1204.8    5059 1206.04    5069 1208.22    5109 1213.63
  5130.6 1214.71  5168.2  1216.5  5280.5 1221.28  5333.8 1222.96  5381.9 1224.44
#Mann= 6 ,-1 , 0
    4674     .12       0  4992.9     .07       0  5005.1     .12       0
  5130.6     .05       0  5168.2     .12       0  5333.8     .05       0
Bank Sta=4992.9,5005.1
XS Rating Curve= 0 ,0
Exp/Cntr=0.3,0.1

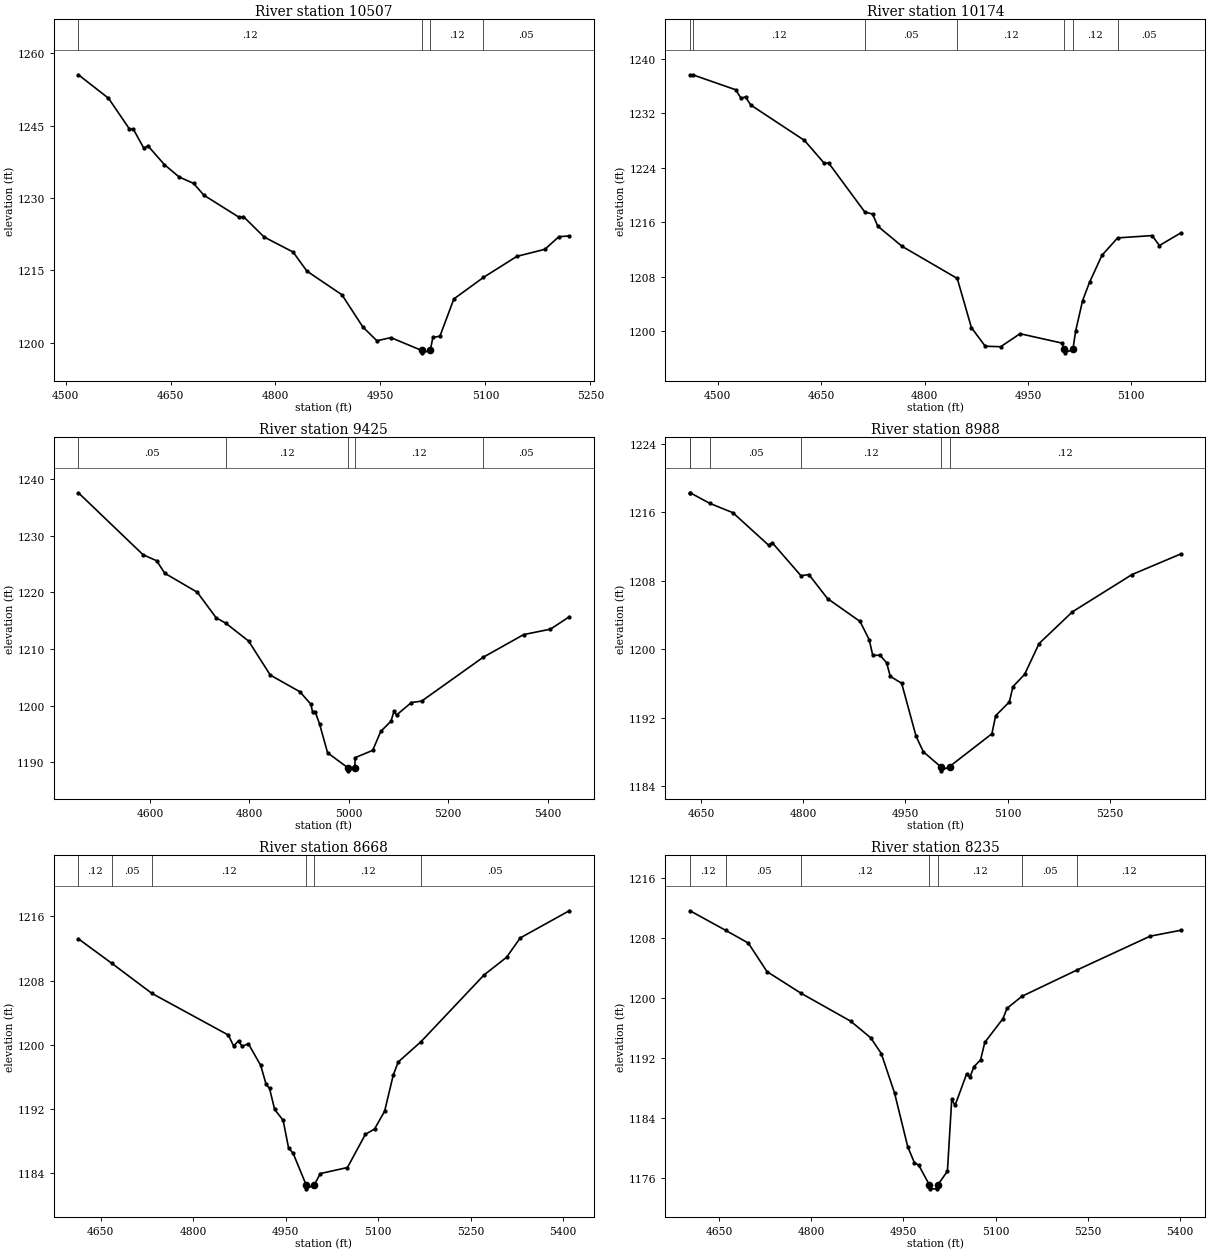
Type RM Length L Ch R = 1 ,10507   ,333,333,333
BEGIN DESCRIPTION:
LOST HOLLOW CREEK 23.0
END DESCRIPTION:
XS GIS Cut Line= 3
      2810705.68     10177003.11      2810460.18     10176827.19
      2810060.91     10176829.36
#Sta/Elev= 30
  4518.4 1255.55  4561.4 1250.69  4590.9  1244.4    4597 1244.24  4611.7 1240.38
  4617.9  1240.8  4641.2 1236.94  4662.1 1234.39    4683 1233.03  4697.7 1230.59
  4748.1    1226  4754.2 1226.16  4783.7 1221.93  4825.2  1218.8  4844.9 1214.85
  4894.9 1209.95  4924.9 1203.26  4944.9 1200.41  4964.9 1201.07  5008.8 1198.41
  5009.3 1197.91  5021.1 1198.41  5024.9 1201.12  5034.9 1201.35  5054.9 1209.09
  5097.2 1213.55  5144.9 1217.91  5184.9 1219.37  5204.9 1221.99  5219.7 1222.14
#Mann= 4 ,-1 , 0
  4518.4     .12       0  5008.8     .07       0  5021.1     .12       0
  5097.2     .05       0
Bank Sta=5008.8,5021.1
XS Rating Curve= 0 ,0
Exp/Cntr=0.3,0.1

Type RM Length L Ch R = 1 ,10174   ,749,749,749
BEGIN DESCRIPTION:
LOST HOLLOW CREEK 22.0
END DESCRIPTION:
XS GIS Cut Line= 3
      2810724.97     10176757.77      2810447.04     10176518.78
      2810104.28     10176473.46
#Sta/Elev= 30
  4459.7 1237.67  4463.6 1237.68  4525.9 1235.48  4533.6 1234.25  4540.2 1234.42
  4547.8 1233.24  4625.8 1228.03  4654.3  1224.7  4660.9 1224.71  4713.3 1217.52
  4724.5 1217.22  4732.2 1215.43  4767.3 1212.48  4847.5 1207.75    4868 1200.53
  4888.1 1197.79  4910.5 1197.72  4938.6 1199.63  4999.1 1198.26    5003 1197.32
  5003.5 1196.82  5015.3 1197.32  5019.3 1200.04  5029.4  1204.5  5039.4 1207.17
  5057.4 1211.14  5080.2 1213.71  5130.2 1214.05  5140.9 1212.59    5172 1214.45
#Mann= 7 ,-1 , 0
  4459.7     .05       0  4463.6     .12       0  4713.3     .05       0
  4847.5     .12       0    5003     .07       0  5015.3     .12       0
  5080.2     .05       0
Bank Sta=5003,5015.3
XS Rating Curve= 0 ,0
Exp/Cntr=0.3,0.1

Type RM Length L Ch R = 1 ,9425    ,437,437,437
BEGIN DESCRIPTION:
LOST HOLLOW CREEK 21.0
END DESCRIPTION:
XS GIS Cut Line= 3
      2811072.19       10176072.      2810657.51     10175844.64
      2810156.38      10175729.1
#Sta/Elev= 30
  4456.2 1237.58  4586.2 1226.64  4613.7 1225.57  4629.8 1223.37  4695.3 1220.01
  4733.2  1215.5  4752.5 1214.55  4798.6 1211.38  4842.2 1205.37  4901.9 1202.42
  4923.7 1200.22  4927.3 1198.86  4932.6 1198.86  4941.3 1196.72  4957.4 1191.65
  4998.8 1188.96  4999.3 1188.46  5011.9 1188.96  5013.1  1190.8  5048.1 1192.08
  5064.4 1195.43  5084.9 1197.23  5090.9 1198.96    5096 1198.32    5126 1200.53
  5146.5 1200.77  5270.3 1208.52  5351.8 1212.53  5405.7 1213.49  5443.4 1215.67
#Mann= 5 ,-1 , 0
  4456.2     .05       0  4752.5     .12       0  4998.8     .07       0
  5011.9     .12       0  5270.3     .05       0
Bank Sta=4998.8,5011.9
XS Rating Curve= 0 ,0
Exp/Cntr=0.3,0.1

Type RM Length L Ch R = 1 ,8988    ,320,320,320
BEGIN DESCRIPTION:
LOST HOLLOW CREEK 20.0
END DESCRIPTION:
XS GIS Cut Line= 3
      2811050.44     10175575.01      2810835.61     10175453.49
       2810389.6     10175295.44
#Sta/Elev= 30
  4634.1 1218.26  4634.3 1218.26  4663.2 1217.02    4697 1215.93  4749.2 1212.15
  4754.9 1212.41  4796.8 1208.57  4808.4 1208.71  4835.8  1205.9  4883.5 1203.23
  4896.9  1201.1  4902.2 1199.26  4912.7 1199.29  4922.5  1198.4  4927.8 1196.82
  4944.5 1196.01  4965.7 1189.81  4976.3 1188.01  5001.5 1186.28    5002 1185.78
  5014.8 1186.28  5076.9 1190.11  5082.4 1192.22  5102.5 1193.83  5107.8 1195.62
  5124.9 1197.05  5146.1 1200.65  5195.1 1204.36  5282.5 1208.71  5354.1 1211.12
#Mann= 6 ,-1 , 0
  4634.1     .05       0  4634.3     .12       0  4663.2     .05       0
  4796.8     .12       0  5001.5     .07       0  5014.8     .12       0
Bank Sta=5001.5,5014.8
XS Rating Curve= 0 ,0
Exp/Cntr=0.3,0.1

Type RM Length L Ch R = 1 ,8668    ,433,433,433
BEGIN DESCRIPTION:
LOST HOLLOW CREEK 19.0
END DESCRIPTION:
XS GIS Cut Line= 3
      2811089.54     10175427.48      2810965.82     10175184.39
       2810503.6     10174939.18
#Sta/Elev= 30
  4614.1  1213.2  4668.5 1210.14  4733.3 1206.41  4857.2 1201.23  4865.9 1199.86
  4873.8 1200.51  4879.4 1199.83  4889.8 1200.14  4909.7 1197.46  4918.5  1195.1
  4924.1 1194.58  4932.3 1191.98  4946.1 1190.62  4954.9  1187.2  4962.4  1186.5
  4983.4 1182.59  4983.9 1182.09  4996.7 1182.59  5006.4 1183.99  5050.4 1184.74
  5079.5 1188.87  5094.4 1189.54  5110.7 1191.75  5124.7 1196.24  5132.7 1197.87
  5169.8 1200.41  5271.9  1208.7  5308.6 1210.91  5330.6 1213.31  5410.1 1216.69
#Mann= 6 ,-1 , 0
  4614.1     .12       0  4668.5     .05       0  4733.3     .12       0
  4983.4     .07       0  4996.7     .12       0  5169.8     .05       0
Bank Sta=4983.4,4996.7
XS Rating Curve= 0 ,0
Exp/Cntr=0.3,0.1

Type RM Length L Ch R = 1 ,8235    ,390,390,390
BEGIN DESCRIPTION:
LOST HOLLOW CREEK 18.0
END DESCRIPTION:
XS GIS Cut Line= 3
      2811447.58     10174952.18       2811221.9     10174819.81
      2810722.79     10174620.17
#Sta/Elev= 30
  4602.6 1211.66  4660.8 1209.04  4697.5 1207.35  4727.9 1203.54  4783.3 1200.65
  4864.2 1196.92  4896.8  1194.7    4914  1192.6  4935.6 1187.33  4957.1 1180.15
  4967.9 1178.03  4974.9 1177.71  4992.5 1175.04    4993 1174.54  5005.3 1174.54
  5005.8 1175.04  5021.7  1176.9  5028.7  1186.5  5034.1 1185.68    5053 1189.89
  5058.4 1189.44  5064.8 1190.84  5075.6 1191.74  5082.6  1194.1  5112.2 1197.27
  5118.7 1198.64  5143.2 1200.25  5232.6 1203.75  5351.8 1208.27  5401.8 1209.06
#Mann= 7 ,-1 , 0
  4602.6     .12       0  4660.8     .05       0  4783.3     .12       0
  4992.5     .07       0  5005.8     .12       0  5143.2     .05       0
  5232.6     .12       0
Bank Sta=4992.5,5005.8
XS Rating Curve= 0 ,0
Exp/Cntr=0.3,0.1

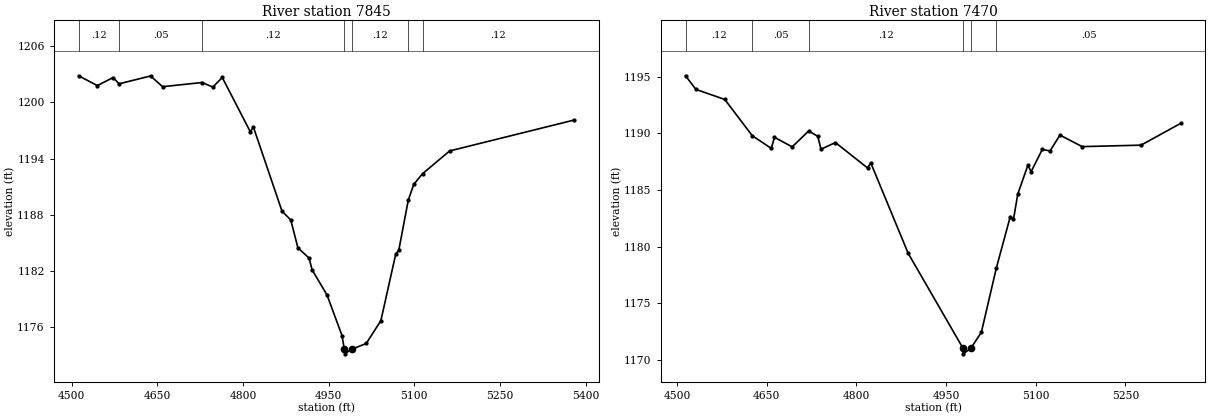
Type RM Length L Ch R = 1 ,7845    ,375,375,375
BEGIN DESCRIPTION:
LOST HOLLOW CREEK 17.0
END DESCRIPTION:
XS GIS Cut Line= 3
      2811686.29     10174546.37      2811317.39     10174433.94
      2810861.62     10174279.43
#Sta/Elev= 30
  4512.3 1202.86  4545.1 1201.81  4572.7 1202.67  4583.1    1202  4638.3 1202.84
  4659.3 1201.69  4728.4 1202.14  4747.3 1201.65  4763.8 1202.68    4813 1196.85
  4818.2 1197.39  4868.4 1188.36  4883.8 1187.41  4896.2 1184.44  4915.8 1183.33
  4921.1 1182.08  4947.3 1179.37  4973.4 1175.04  4977.5 1173.58    4978 1173.08
  4990.9 1173.58  5015.9 1174.19  5041.5 1176.64  5067.6 1183.79  5072.9 1184.19
  5089.4 1189.52    5099 1191.23  5114.4 1192.37  5161.9 1194.81  5379.2 1198.11
#Mann= 7 ,-1 , 0
  4512.3     .12       0  4583.1     .05       0  4728.4     .12       0
  4977.5     .07       0  4990.9     .12       0  5089.4     .05       0
  5114.4     .12       0
Bank Sta=4977.5,4990.9
XS Rating Curve= 0 ,0
Exp/Cntr=0.3,0.1

Type RM Length L Ch R = 1 ,7470    ,166,166,166
BEGIN DESCRIPTION:
LOST HOLLOW CREEK 16.0
END DESCRIPTION:
XS GIS Cut Line= 3
       2811770.9     10174223.01      2811169.81     10173979.97
      2811005.64     10174053.13
#Sta/Elev= 30
  4514.2 1195.08  4531.6 1193.88  4579.9 1192.99  4625.9 1189.79  4657.6 1188.68
    4663 1189.65  4692.6 1188.81  4720.2 1190.21  4735.4 1189.74  4740.8  1188.6
  4764.9 1189.19  4818.6 1186.95    4824  1187.4  4886.6 1179.42  4978.2 1171.05
  4978.7 1170.55  4991.6 1171.05    5009 1172.45  5034.2 1178.15  5057.3 1182.65
  5062.7 1182.41  5069.9 1184.64  5086.8 1187.19  5092.2 1186.62  5110.9 1188.58
  5123.9 1188.45  5140.4 1189.85  5177.6 1188.83    5276 1188.96  5342.3 1190.88
#Mann= 6 ,-1 , 0
  4514.2     .12       0  4625.9     .05       0  4720.2     .12       0
  4978.2     .07       0  4991.6     .12       0  5034.2     .05       0
Bank Sta=4978.2,4991.6
XS Rating Curve= 0 ,0
Exp/Cntr=0.3,0.1