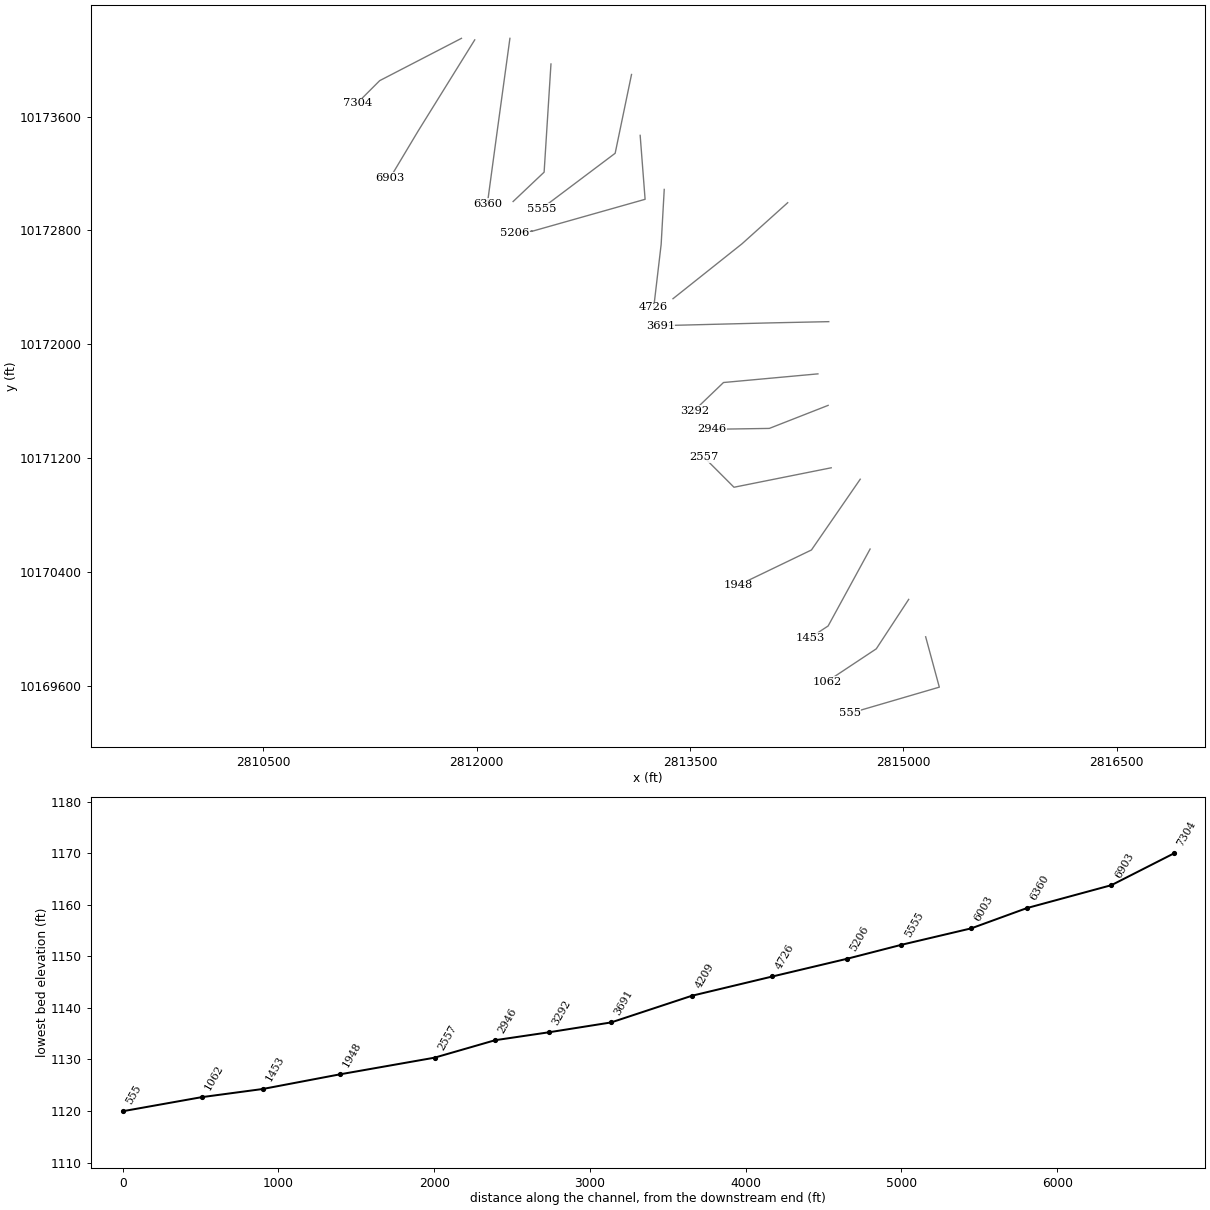
HEC-RAS study LOST HOLLOW CREEK.prj: LOST HOLLOW CREEK Base Level Engineering

--- LOST HOLLOW CREEK.g01 (geometry) --- (continued)

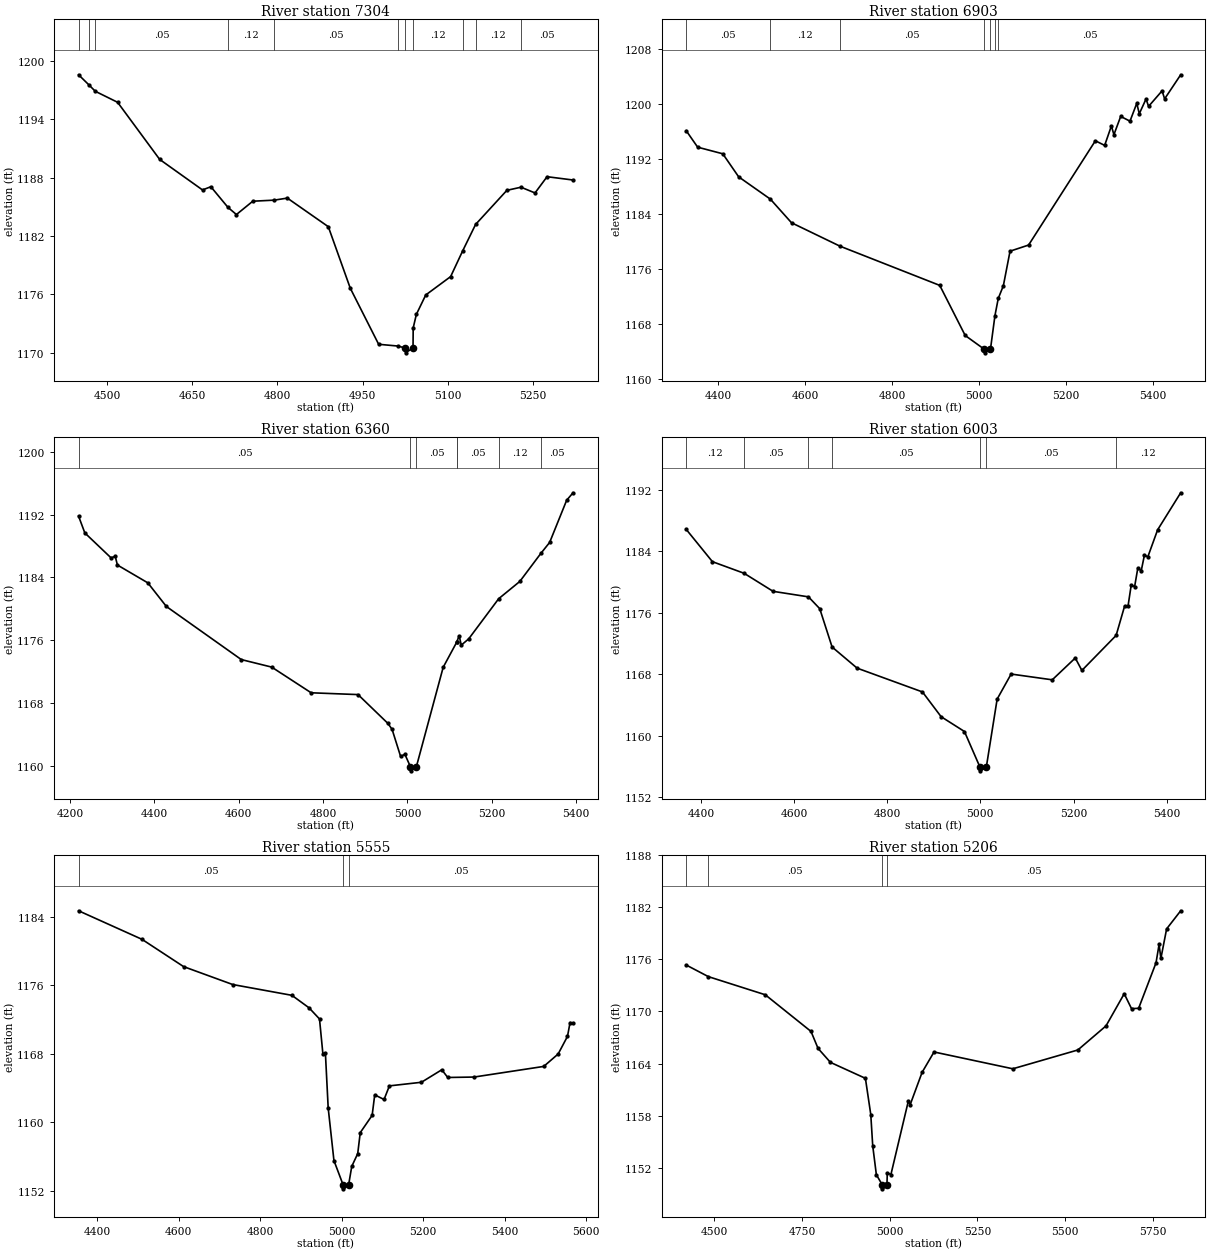
Type RM Length L Ch R = 1 ,7304    ,401,401,401
BEGIN DESCRIPTION:
LOST HOLLOW CREEK 15.0
END DESCRIPTION:
XS GIS Cut Line= 3
      2811892.48     10174149.24      2811317.38     10173851.93
      2811159.84     10173694.39
#Sta/Elev= 30
  4450.1 1198.57  4468.3 1197.53  4479.6 1196.87  4518.8 1195.74  4592.8 1189.87
  4668.2 1186.73  4682.9 1187.06  4713.1 1184.93  4727.9  1184.2  4756.7 1185.57
  4794.4 1185.68  4817.5 1185.89  4889.6 1182.95  4928.3 1176.62  4978.2 1170.86
  5011.8 1170.68    5025 1170.48  5025.5 1169.98  5038.7 1170.48    5039 1172.54
  5044.6 1173.94  5061.1 1175.93  5104.9 1177.82  5125.8 1180.43  5148.8 1183.18
  5203.9 1186.69  5228.7 1187.01  5253.4 1186.42  5274.6 1188.09  5320.3 1187.75
#Mann= 11 ,-1 , 0
  4450.1     .05       0  4468.3     .12       0  4479.6     .05       0
  4713.1     .12       0  4794.4     .05       0  5011.8     .12       0
    5025     .05       0  5038.7     .12       0  5125.8     .05       0
  5148.8     .12       0  5228.7     .05       0
Bank Sta=5025,5038.7
XS Rating Curve= 0 ,0
Exp/Cntr=0.3,0.1

Type RM Length L Ch R = 1 ,6903    ,543,543,543
BEGIN DESCRIPTION:
LOST HOLLOW CREEK 14.0
END DESCRIPTION:
XS GIS Cut Line= 3
       2811985.8     10174138.42      2811587.23     10173497.26
      2811390.41     10173168.52
#Sta/Elev= 30
  4326.6 1196.09  4352.9  1193.7  4410.7 1192.74  4447.3 1189.39  4520.3 1186.15
  4568.9 1182.72  4680.4 1179.32  4910.1 1173.62  4968.7 1166.34  5013.1 1164.32
  5013.6 1163.82  5026.8 1164.32  5037.2 1169.24  5044.8 1171.73  5056.5 1173.56
  5071.9 1178.59  5114.6 1179.48  5268.3 1194.63  5289.7 1193.96  5305.2 1196.79
    5311 1195.52  5326.6 1198.17    5348 1197.48  5363.6 1200.07  5369.4 1198.56
  5384.9  1200.7  5390.8 1199.63  5421.9 1201.89  5427.7 1200.72  5464.7 1204.22
#Mann= 7 ,-1 , 0
  4326.6     .05       0  4520.3     .12       0  4680.4     .05       0
  5013.1     .05       0  5026.8     .05       0  5037.2     .12       0
  5044.8     .05       0
Bank Sta=5013.1,5026.8
XS Rating Curve= 0 ,0
Exp/Cntr=0.3,0.1

Type RM Length L Ch R = 1 ,6360    ,357,357,357
BEGIN DESCRIPTION:
LOST HOLLOW CREEK 13.0
END DESCRIPTION:
XS GIS Cut Line= 3
      2812233.18     10174149.23      2812144.21     10173500.37
      2812074.76     10172988.19
#Sta/Elev= 30
  4220.6  1191.8  4235.4 1189.67  4297.4  1186.5  4307.5 1186.68  4312.6 1185.58
  4384.7 1183.31  4428.7  1180.3  4606.2 1173.54  4678.3 1172.58  4771.8 1169.31
  4882.9 1169.08  4953.5 1165.42  4963.6 1164.65  4983.8  1161.2  4993.9 1161.48
  5007.2 1159.87  5007.7 1159.37    5021 1159.87  5084.7 1172.56  5116.4 1175.72
  5116.6 1175.75  5122.5 1176.57  5127.6 1175.38  5145.2 1176.18  5216.2 1181.29
  5266.3 1183.49    5316 1187.05    5337 1188.46  5377.3 1193.83  5392.4 1194.78
#Mann= 7 ,-1 , 0
  4220.6     .05       0  5007.2     .05       0    5021     .05       0
  5116.4     .12       0  5116.6     .05       0  5216.2     .12       0
    5316     .05       0
Bank Sta=5007.2,5021
XS Rating Curve= 0 ,0
Exp/Cntr=0.3,0.1

Type RM Length L Ch R = 1 ,6003    ,448,448,448
BEGIN DESCRIPTION:
LOST HOLLOW CREEK 12.0
END DESCRIPTION:
XS GIS Cut Line= 3
      2812521.81     10173969.15      2812473.67     10173209.28
      2812255.71     10173003.13
#Sta/Elev= 30
  4368.7 1186.87  4424.9 1182.67  4492.9 1181.16  4555.1 1178.81  4631.1 1178.09
  4655.3 1176.55  4681.8 1171.56  4735.5 1168.81  4875.8 1165.71  4915.8 1162.49
  4965.9 1160.56  4999.1 1155.94  4999.6 1155.44  5012.9 1155.94  5036.1 1164.78
  5066.1 1168.04  5154.4 1167.29  5203.8 1170.13    5218 1168.51  5291.5 1173.07
  5309.8 1176.91  5317.1 1176.91  5323.9 1179.63  5331.2 1179.42  5338.1 1181.85
  5345.4 1181.49  5352.3 1183.54  5359.5 1183.29  5380.6 1186.82  5430.1 1191.64
#Mann= 7 ,-1 , 0
  4368.7     .12       0  4492.9     .05       0  4631.1     .12       0
  4681.8     .05       0  4999.1     .05       0  5012.9     .05       0
  5291.5     .12       0
Bank Sta=4999.1,5012.9
XS Rating Curve= 0 ,0
Exp/Cntr=0.3,0.1

Type RM Length L Ch R = 1 ,5555    ,349,349,349
BEGIN DESCRIPTION:
LOST HOLLOW CREEK 11.0
END DESCRIPTION:
XS GIS Cut Line= 3
      2813088.21      10173895.3       2812973.2     10173341.95
      2812455.67      10172953.1
#Sta/Elev= 30
  4354.8 1184.71  4510.2 1181.38  4612.4 1178.19  4732.8  1176.1  4877.9 1174.84
    4920 1173.38  4945.6 1172.08  4953.9 1168.01  4960.1 1168.06  4966.9 1161.69
    4981 1155.55  5003.2 1152.75  5003.7 1152.25  5017.1 1152.75  5024.7 1154.87
  5039.3 1156.36  5045.5 1158.81  5074.7 1160.83    5081 1163.22  5103.9 1162.68
    5117 1164.27  5195.5 1164.69  5245.5 1166.15  5260.1 1165.25  5324.6  1165.3
  5495.4 1166.54  5530.8 1167.99  5553.7 1170.05    5560 1171.66  5567.3 1171.57
#Mann= 3 ,-1 , 0
  4354.8     .05       0  5003.2     .05       0  5017.1     .05       0
Bank Sta=5003.2,5017.1
XS Rating Curve= 0 ,0
Exp/Cntr=0.3,0.1

Type RM Length L Ch R = 1 ,5206    ,480,480,480
BEGIN DESCRIPTION:
Mapping XS 726be8ed
END DESCRIPTION:
XS GIS Cut Line= 5
      2813148.98     10173467.77       2813183.7      10173018.6
      2812385.09      10172792.9      2812389.43     10172795.07
      2812265.77     10172782.05
#Sta/Elev= 30
  4420.2 1175.36  4483.4 1174.02  4645.5 1171.93  4775.9  1167.7    4796 1165.74
  4831.3 1164.13    4931 1162.29  4946.3 1158.11  4951.8 1154.52  4962.2 1151.17
  4978.5 1150.04    4979 1149.54  4992.4 1150.04  4993.4 1151.38  5003.7 1151.19
  5053.4 1159.67  5058.6 1159.25  5092.6 1162.98  5126.6 1165.33  5351.2 1163.39
  5536.6 1165.56  5616.9 1168.34  5668.8 1172.05  5689.6 1170.33  5709.9 1170.37
  5759.5 1175.62  5768.2 1177.74  5773.3 1176.12  5789.7 1179.53  5829.8 1181.62
#Mann= 4 ,-1 , 0
  4420.2     .12       0  4483.4     .05       0  4978.5     .05       0
  4992.4     .05       0
Bank Sta=4978.5,4992.4
XS Rating Curve= 0 ,0
Exp/Cntr=0.3,0.1

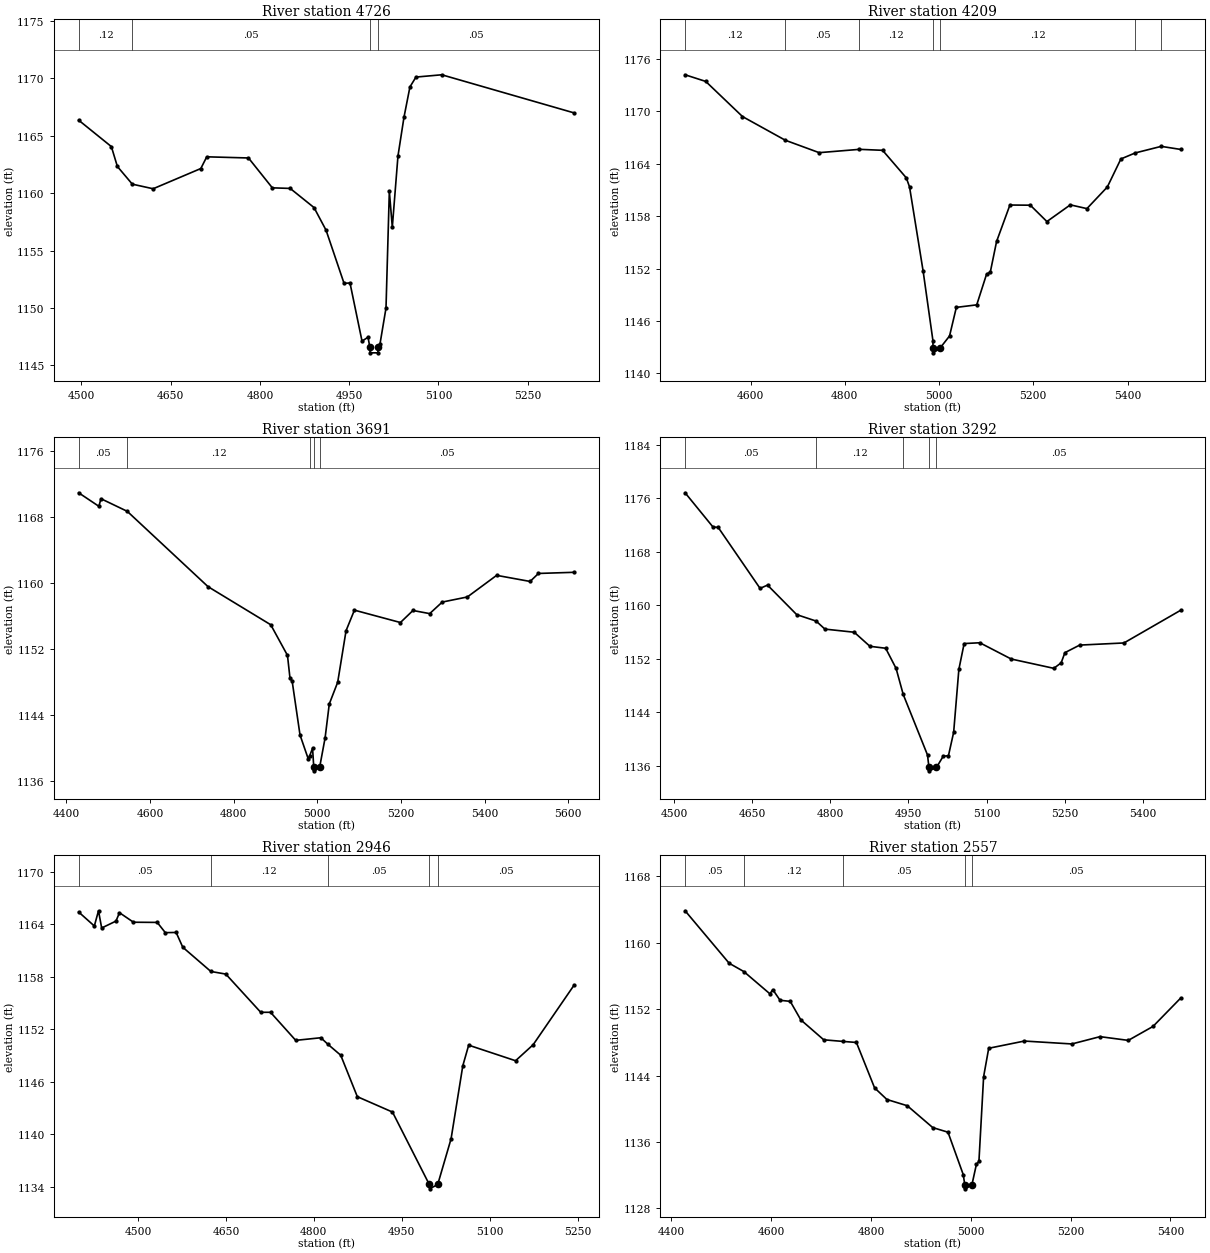
Type RM Length L Ch R = 1 ,4726    ,517,517,517
BEGIN DESCRIPTION:
LOST HOLLOW CREEK 10.0
END DESCRIPTION:
XS GIS Cut Line= 3
      2813318.25     10173088.07      2813296.55     10172701.75
      2813244.46     10172259.03
#Sta/Elev= 30
  4495.3 1166.35  4550.3 1164.05  4560.4 1162.32  4585.5 1160.78  4620.5 1160.38
  4700.6 1162.14  4710.6 1163.16  4780.7 1163.06  4820.8 1160.46  4850.8 1160.41
  4890.9 1158.74  4911.1 1156.77  4941.3 1152.15  4951.3 1152.18  4971.5 1147.12
  4981.6 1147.46  4984.6  1146.6  4985.1  1146.1  4998.1  1146.1  4998.6  1146.6
  5001.7 1146.87  5011.8    1150  5017.4 1160.16  5022.4 1157.04  5031.9 1163.23
    5042  1166.6    5052 1169.24  5062.1  1170.1  5105.5  1170.3    5328 1166.98
#Mann= 4 ,-1 , 0
  4495.3     .12       0  4585.5     .05       0  4984.6     .05       0
  4998.6     .05       0
Bank Sta=4984.6,4998.6
XS Rating Curve= 0 ,0
Exp/Cntr=0.3,0.1

Type RM Length L Ch R = 1 ,4209    ,518,518,518
BEGIN DESCRIPTION:
LOST HOLLOW CREEK 9.0
END DESCRIPTION:
XS GIS Cut Line= 3
      2814186.29      10172994.7      2813865.13      10172706.1
      2813379.87     10172320.49
#Sta/Elev= 30
  4461.1 1174.17  4504.9 1173.41  4582.9 1169.39  4673.8 1166.68  4745.6 1165.26
  4831.1 1165.64  4880.2 1165.53  4930.5 1162.38  4937.4 1161.34  4966.2 1151.72
    4987 1143.77  4987.2 1142.86  4987.7 1142.36  5001.5 1142.86  5022.3 1144.29
  5036.7 1147.56    5080 1147.85  5100.8 1151.35  5108.8  1151.6  5122.1  1155.1
  5150.4 1159.27  5193.7 1159.25  5228.9 1157.38  5278.6 1159.29  5313.8 1158.86
  5357.1 1161.33  5385.9 1164.54  5416.4 1165.23  5471.5 1165.98  5512.7 1165.63
#Mann= 7 ,-1 , 0
  4461.1     .12       0  4673.8     .05       0  4831.1     .12       0
  4987.2     .05       0  5001.5     .12       0  5416.4     .12       0
  5471.5     .05       0
Bank Sta=4987.2,5001.5
XS Rating Curve= 0 ,0
Exp/Cntr=0.3,0.1

Type RM Length L Ch R = 1 ,3691    ,399,399,399
BEGIN DESCRIPTION:
LOST HOLLOW CREEK 8.0
END DESCRIPTION:
XS GIS Cut Line= 3
      2814474.98     10172159.22      2814064.78     10172150.54
      2813290.32     10172131.02
#Sta/Elev= 30
  4429.4  1170.9  4477.8 1169.26  4482.8 1170.18  4545.7 1168.65  4738.8 1159.52
  4888.8  1154.9  4928.8 1151.19  4934.9 1148.39  4939.9  1148.1  4958.8 1141.54
  4978.8 1138.59  4981.9 1139.01  4988.8 1139.93  4991.6 1137.69  4992.1 1137.19
    5006 1137.69  5018.8 1141.19  5028.8  1145.3  5048.9 1147.93  5068.9 1154.18
  5088.9 1156.67  5198.9 1155.17  5228.9 1156.63  5268.9 1156.25  5298.9 1157.65
    5359 1158.27    5429 1160.89    5509 1160.15    5529 1161.12  5614.4 1161.26
#Mann= 5 ,-1 , 0
  4429.4     .05       0  4545.7     .12       0  4981.9     .05       0
  4991.6     .05       0    5006     .05       0
Bank Sta=4991.6,5006
XS Rating Curve= 0 ,0
Exp/Cntr=0.3,0.1

Type RM Length L Ch R = 1 ,3292    ,346,346,346
BEGIN DESCRIPTION:
LOST HOLLOW CREEK 7.0
END DESCRIPTION:
XS GIS Cut Line= 3
      2814398.95     10171792.46      2813734.92      10171731.7
      2813529.69     10171535.11
#Sta/Elev= 30
  4521.4 1176.81  4574.9  1171.7  4584.9 1171.64  4665.3 1162.53  4679.6 1163.02
  4735.6 1158.61  4772.8 1157.65  4789.7 1156.45    4846 1155.98  4876.1 1153.88
  4906.3 1153.59  4926.3 1150.58    4940 1146.69  4986.6 1137.65  4989.4 1135.78
  4989.9 1135.28  5003.8 1135.78  5016.7 1137.46  5026.8 1137.54  5036.8 1141.04
  5046.8 1150.44  5056.9 1154.29    5087 1154.41  5147.3 1151.98    5229 1150.59
  5243.1 1151.41  5250.3 1152.93  5278.6 1154.06  5363.6 1154.38  5472.4 1159.26
#Mann= 5 ,-1 , 0
  4521.4     .05       0  4772.8     .12       0    4940     .05       0
  4989.4     .05       0  5003.8     .05       0
Bank Sta=4989.4,5003.8
XS Rating Curve= 0 ,0
Exp/Cntr=0.3,0.1

Type RM Length L Ch R = 1 ,2946    ,389,389,389
BEGIN DESCRIPTION:
LOST HOLLOW CREEK 6.0
END DESCRIPTION:
XS GIS Cut Line= 3
      2814470.61     10171571.12       2814057.1     10171409.33
      2813655.68     10171403.11
#Sta/Elev= 30
  4398.7  1165.4  4425.5  1163.8  4432.6 1165.54    4438 1163.57  4462.4 1164.36
  4468.4 1165.32  4492.3 1164.23  4532.8 1164.21  4546.6 1163.04  4565.1 1163.06
  4576.4 1161.37  4624.3  1158.6  4649.8  1158.3  4709.4 1153.93  4726.1 1153.93
  4769.1 1150.72    4812 1151.02  4824.2 1150.26  4845.9 1149.02  4874.2 1144.28
  4934.2 1142.52    4997 1134.24  4997.5 1133.74  5011.4 1134.24  5034.2 1139.47
  5054.2 1147.82  5064.2 1150.17  5144.2 1148.39  5174.2 1150.22  5244.2 1157.05
#Mann= 5 ,-1 , 0
  4398.7     .05       0  4624.3     .12       0  4824.2     .05       0
    4997     .05       0  5011.4     .05       0
Bank Sta=4997,5011.4
XS Rating Curve= 0 ,0
Exp/Cntr=0.3,0.1

Type RM Length L Ch R = 1 ,2557    ,609,609,609
BEGIN DESCRIPTION:
LOST HOLLOW CREEK 5.0
END DESCRIPTION:
XS GIS Cut Line= 3
      2814492.27     10171132.74       2813808.7     10170996.03
      2813599.48     10171205.25
#Sta/Elev= 30
  4427.4 1163.84  4515.7 1157.52  4545.1 1156.52  4597.3 1153.84  4603.2 1154.34
  4617.7 1153.06  4638.1 1152.93  4659.3  1150.7  4705.2  1148.3  4744.8  1148.1
  4770.7 1147.98  4807.1 1142.51  4831.8 1141.11  4872.6 1140.36  4923.6 1137.73
  4954.2 1137.17  4984.8 1132.06  4987.8 1130.85  4988.3 1130.35  5002.2 1130.85
  5011.1 1133.29  5016.2 1133.65  5025.6 1143.86  5035.8 1147.28  5107.2 1148.15
  5202.4  1147.8  5258.9 1148.68  5315.5 1148.23    5365 1149.91  5420.4 1153.32
#Mann= 5 ,-1 , 0
  4427.4     .05       0  4545.1     .12       0  4744.8     .05       0
  4987.8     .05       0  5002.2     .05       0
Bank Sta=4987.8,5002.2
XS Rating Curve= 0 ,0
Exp/Cntr=0.3,0.1

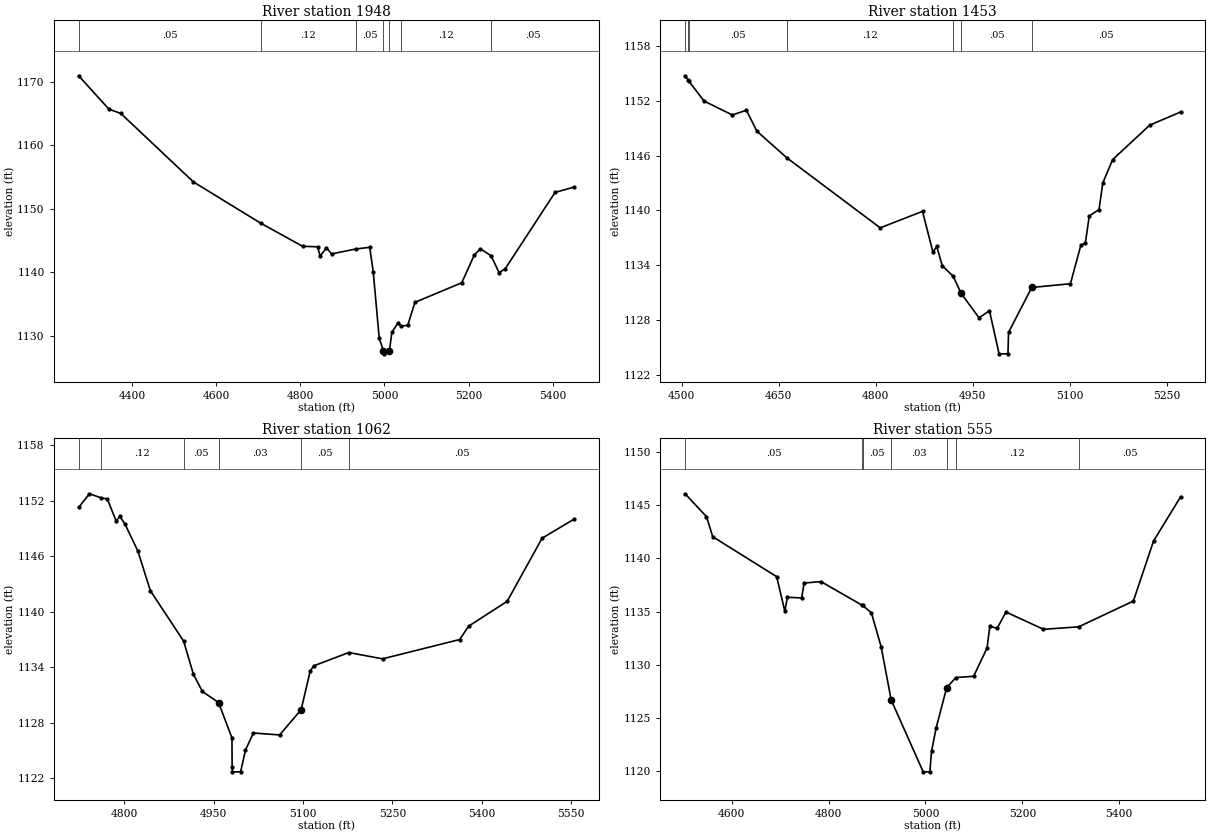
Type RM Length L Ch R = 1 ,1948    ,495,495,495
BEGIN DESCRIPTION:
LOST HOLLOW CREEK 4.0
END DESCRIPTION:
XS GIS Cut Line= 3
      2814696.27     10171052.43      2814353.41     10170555.49
      2813834.77     10170305.93
#Sta/Elev= 30
  4272.1 1170.97  4344.2  1165.7  4372.3 1165.04  4545.4 1154.22  4705.6 1147.71
    4805 1144.08  4840.8 1143.99  4846.9 1142.54  4861.8 1143.82  4874.3 1142.87
  4931.7 1143.65  4964.8 1143.91  4973.2 1140.05  4987.5 1129.55  4997.4 1127.61
  4997.9 1127.11  5011.8 1127.61  5017.6 1130.54  5032.7 1132.04    5039 1131.47
  5055.4 1131.62  5072.4 1135.23    5184 1138.33  5213.8 1142.72  5228.4 1143.67
  5253.7 1142.57  5272.8 1139.91  5287.2 1140.52    5406 1152.58  5451.4 1153.42
#Mann= 7 ,-1 , 0
  4272.1     .05       0  4705.6     .12       0  4931.7     .05       0
  4997.4     .05       0  5011.8     .05       0    5039     .12       0
  5253.7     .05       0
Bank Sta=4997.4,5011.8
XS Rating Curve= 0 ,0
Exp/Cntr=0.3,0.1

Type RM Length L Ch R = 1 ,1453    ,391,391,391
BEGIN DESCRIPTION:
LOST HOLLOW CREEK 3.0
END DESCRIPTION:
XS GIS Cut Line= 3
      2814765.74     10170562.02      2814470.59     10170021.63
      2814344.73     10169939.17
#Sta/Elev= 30
  4505.3 1154.77  4510.5 1154.28  4511.1 1154.18  4534.6    1152  4578.3 1150.47
  4600.1 1150.99  4616.2  1148.7  4662.8 1145.76    4807 1138.09  4872.4  1139.9
  4888.6 1135.39  4894.3 1136.06  4902.9 1133.94  4919.8 1132.78  4932.2 1130.89
  4959.8 1128.22  4975.9    1129  4990.8 1124.27  5004.5 1124.27  5005.4 1126.62
  5041.3 1131.55  5101.1 1131.96  5117.2 1136.18  5124.2 1136.42  5130.2 1139.39
  5145.3  1140.1  5151.2 1143.02  5166.3 1145.57  5223.6 1149.35  5271.5  1150.8
#Mann= 7 ,-1 , 0
  4505.3     .05       0  4510.5     .12       0  4511.1     .05       0
  4662.8     .12       0  4919.8     .05       0  4932.2     .05       0
  5041.3     .05       0
Bank Sta=4932.2,5041.3
XS Rating Curve= 0 ,0
Exp/Cntr=0.3,0.1

Type RM Length L Ch R = 1 ,1062    ,507,507,507
BEGIN DESCRIPTION:
LOST HOLLOW CREEK 2.0
END DESCRIPTION:
XS GIS Cut Line= 3
      2815037.02      10170208.3      2814809.14     10169861.04
      2814461.88     10169630.99
#Sta/Elev= 30
  4723.4 1151.28  4741.6 1152.76  4761.2 1152.32  4771.4 1152.21  4786.5 1149.81
  4792.5 1150.31  4801.4 1149.46  4822.7 1146.59  4843.8 1142.28  4899.7 1136.82
  4916.1 1133.24  4931.2 1131.38  4958.3 1130.18  4980.8 1126.36  4981.1 1123.19
  4981.6 1122.69  4995.3 1122.69  5003.5 1125.04  5016.7 1126.89  5060.8 1126.68
  5096.9  1129.4    5112 1133.55    5118 1134.15  5176.9 1135.59  5233.7 1134.91
  5363.1    1137  5378.1 1138.44  5442.8 1141.13  5501.5 1147.96  5555.3 1150.02
#Mann= 6 ,-1 , 0
  4723.4     .05       0  4761.2     .12       0  4899.7     .05       0
  4958.3     .03       0  5096.9     .05       0  5176.9     .05       0
Bank Sta=4958.3,5096.9
XS Rating Curve= 0 ,0
Exp/Cntr=0.3,0.1

Type RM Length L Ch R = 1 ,555     ,0,0,0
BEGIN DESCRIPTION:
LOST HOLLOW CREEK 1.0
END DESCRIPTION:
XS GIS Cut Line= 3
      2815156.37     10169945.64      2815252.42     10169591.91
      2814622.01     10169407.72
#Sta/Elev= 30
  4503.6 1146.06  4547.7 1143.92  4560.7 1142.03  4692.7 1138.28  4709.6 1135.03
  4714.8 1136.35  4744.2 1136.28  4749.4 1137.68    4784 1137.82  4869.9 1135.58
  4870.2 1135.58  4888.2  1134.9  4908.4  1131.7  4929.2  1126.7  4995.3 1119.96
    5009 1119.96  5012.6 1121.92  5022.1  1124.1  5043.8 1127.86  5062.7 1128.81
  5099.4 1128.93  5127.2 1131.59  5132.8 1133.61    5148 1133.44  5166.3 1134.96
  5243.6 1133.34  5316.3 1133.57  5429.3 1135.99    5471 1141.63  5526.9 1145.78
#Mann= 7 ,-1 , 0
  4503.6     .05       0  4869.9     .12       0  4870.2     .05       0
  4929.2     .03       0  5043.8     .05       0  5062.7     .12       0
  5316.3     .05       0
Bank Sta=4929.2,5043.8
XS Rating Curve= 0 ,0
Exp/Cntr=0.3,0.1

Chan Stop Cuts=-1
Use User Specified Reach Order=0
Composite Channel Slope=5