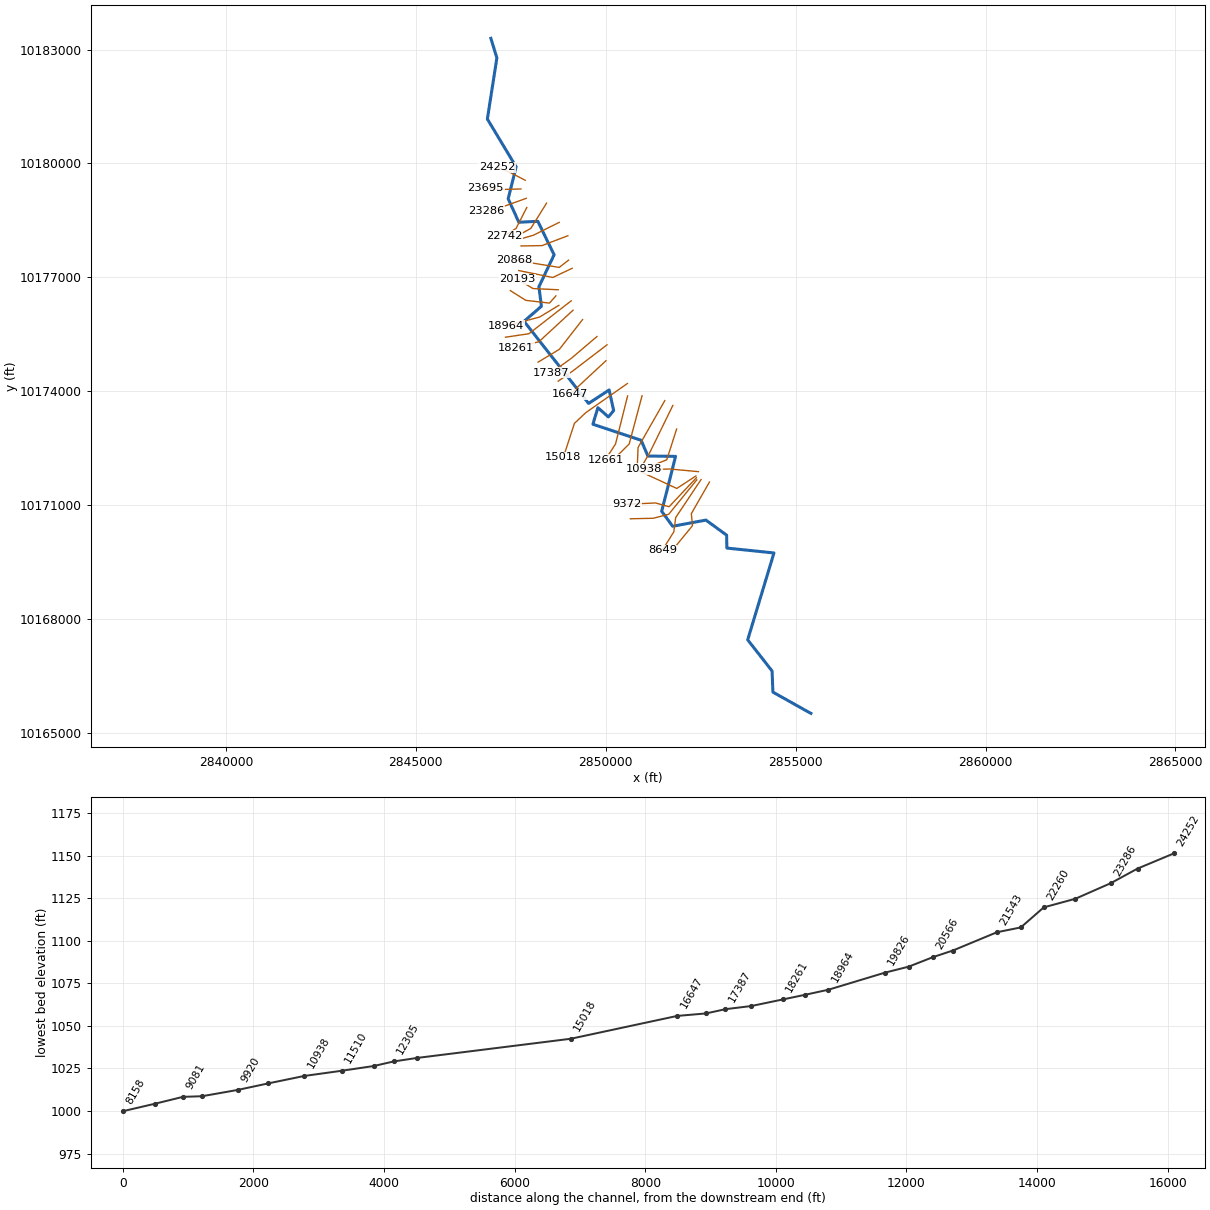
--- BARNETT BRANCH.prj (project) ---

Proj Title=BARNETT BRANCH Base Level Engineering
Current Plan=p01
Default Exp/Contr=0.3,0.1
English Units
Geom File=g01
Flow File=f01
Plan File=p01
BEGIN DESCRIPTION:
BARNETT BRANCH
END DESCRIPTION:

--- BARNETT BRANCH.p01 (plan) ---

Plan Title=Multiple Run
Short Identifier=Multiple
Geom File=g01
Flow File=f01
Subcritical Flow
K Sum by GR= 0
Std Step Tol= 0.01
Critical Tol= 0.01
Num of Std Step Trials= 20
Max Error Tol= 0.3
Flow Tol Ratio= 0.001
Split Flow NTrial= 30
Split Flow Tol= 0.02
Split Flow Ratio= 0.02
Log Output Level= 0
Friction Slope Method= 1
Unsteady Friction Slope Method= 2
Unsteady Bridges Friction Slope Method= 1
Parabolic Critical Depth
Global Vel Dist=  1 , 1 , 1
Global Log Level= 0
CheckData=True
Encroach Param= -1, 0, 0, 0
BEGIN DESCRIPTION:
Multiple Run
END DESCRIPTION:

--- BARNETT BRANCH.f01 (steady flow) ---

Flow Title=Multiple
Number of Profiles=7
Profile Names=10-year,25-year,50-year,1pct_min,100-year,1pct_plu,500-year
River Rch & RM= BARNETT BRANCH,Reach-1,24252
      75     136     209     108     325     983     852
River Rch & RM= BARNETT BRANCH,Reach-1,23695
     106     214     342     181     547    1652    1497
River Rch & RM= BARNETT BRANCH,Reach-1,12661
     240     530     885     485    1464    4421    4257
River Rch & RM= BARNETT BRANCH,Reach-1,5829
     334     755    1276     706    2133    6441    6324
Boundary for River Rch & Prof#=BARNETT BRANCH,Reach-1,1
Up Type=0
Dn Type=3
Dn Slope=0.005
Boundary for River Rch & Prof#=BARNETT BRANCH,Reach-1,2
Up Type=0
Dn Type=3
Dn Slope=0.005
Boundary for River Rch & Prof#=BARNETT BRANCH,Reach-1,3
Up Type=0
Dn Type=3
Dn Slope=0.005
Boundary for River Rch & Prof#=BARNETT BRANCH,Reach-1,4
Up Type=0
Dn Type=3
Dn Slope=0.005
Boundary for River Rch & Prof#=BARNETT BRANCH,Reach-1,5
Up Type=0
Dn Type=3
Dn Slope=0.005
Boundary for River Rch & Prof#=BARNETT BRANCH,Reach-1,6
Up Type=0
Dn Type=3
Dn Slope=0.005
Boundary for River Rch & Prof#=BARNETT BRANCH,Reach-1,7
Up Type=0
Dn Type=3
Dn Slope=0.005

--- BARNETT BRANCH.g01 (geometry) ---

Geom Title=Existing Conditions

River Reach=BARNETT BRANCH,Reach-1
Reach XY= 30
      2846976.00     10183297.00      2847134.25     10182782.00
      2846883.75     10181171.00      2847640.25     10179912.00
      2847431.50     10179071.00      2847712.75     10178452.00
      2848212.75     10178477.00      2848640.75     10177595.00
      2848240.75     10176752.00      2848306.50     10176239.00
      2847850.25     10175842.00      2849548.25     10173679.00
      2850090.00     10174034.00      2850208.75     10173491.00
      2850069.75     10173324.00      2849793.75     10173567.00
      2849662.25     10173131.00      2850932.50     10172709.00
      2851109.75     10172294.00      2851839.25     10172284.00
      2851473.50     10170838.00      2851761.75     10170443.00
      2852637.75     10170606.00      2853182.75     10170209.00
      2853188.75     10169869.00      2854429.50     10169740.00
      2853737.75     10167452.00      2854380.25     10166630.00
      2854401.50     10166074.00      2855400.50     10165514.00

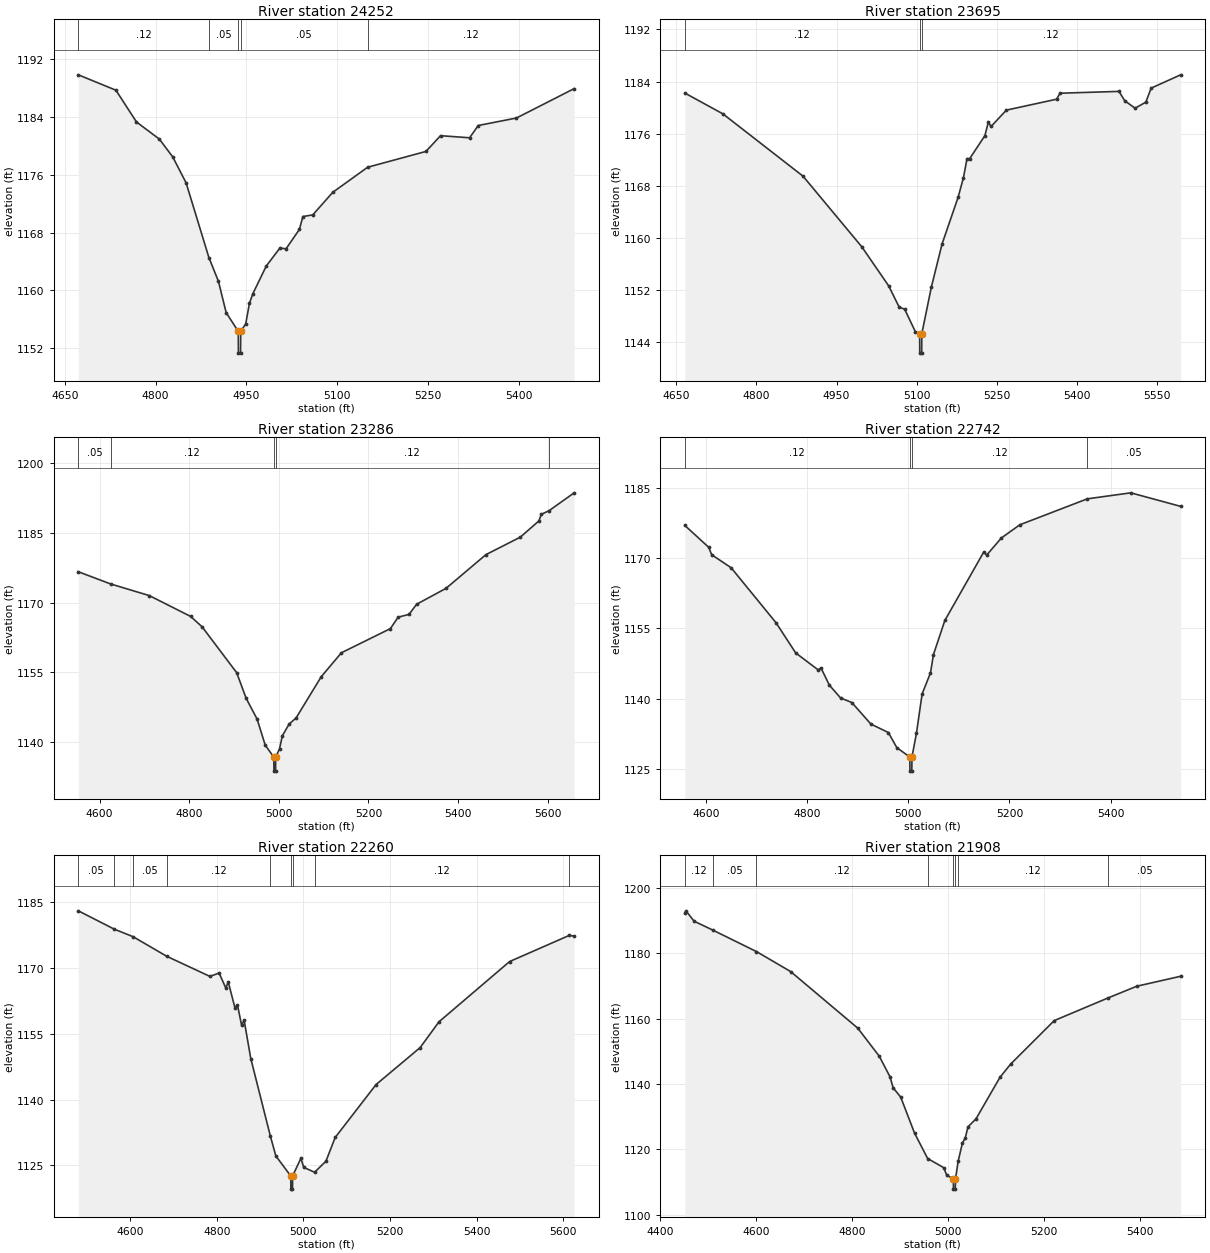
Type RM Length L Ch R = 1,24252,557,557,557
BEGIN DESCRIPTION:
BARNETT BRANCH 44.0
END DESCRIPTION:
XS GIS Cut Line= 3
      2847880.83     10179556.72      2847505.68     10179753.11
      2847138.97     10179902.71
#Sta/Elev= 30
  4672.3 1189.85  4734.4 1187.72  4768.4 1183.32  4806.3 1180.94  4828.4 1178.47
  4850.4 1174.89  4888.1 1164.54  4903.9 1161.24  4916.6 1156.92  4936.7 1154.30
  4936.9 1151.30  4940.4 1151.30  4940.7 1154.30  4949.0 1155.37  4955.1 1158.20
  4960.8 1159.54  4982.9 1163.36  5005.4 1165.85  5015.7 1165.76  5037.8 1168.45
  5043.4 1170.22  5059.8 1170.45  5092.9 1173.58  5150.5 1177.05  5246.9 1179.24
  5270.9 1181.42  5319.0 1181.13  5333.3 1182.83  5396.5 1183.87  5491.8 1187.94
#Mann=5,-1,0
  4672.3    0.12       0  4888.1    0.05       0  4936.7    0.05       0
  4940.7    0.05       0  5150.5    0.12       0
Bank Sta=4936.7,4940.7
Exp/Cntr=0.3,0.1

Type RM Length L Ch R = 1,23695,409,409,409
BEGIN DESCRIPTION:
BARNETT BRANCH 43.0
END DESCRIPTION:
XS GIS Cut Line= 3
      2847766.85     10179328.60      2847237.64     10179314.92
      2846840.80     10179346.85
#Sta/Elev= 30
  4666.2 1182.25  4737.4 1179.06  4887.4 1169.50  4997.5 1158.65  5047.5 1152.69
  5067.2 1149.43  5077.5 1149.10  5097.5 1145.65  5105.5 1145.37  5105.7 1142.37
  5109.3 1142.37  5109.6 1145.37  5127.5 1152.52  5147.5 1159.12  5177.5 1166.27
  5187.5 1169.29  5194.1 1172.19  5199.1 1172.19  5227.6 1175.72  5234.0 1177.79
  5239.1 1177.12  5267.8 1179.63  5361.6 1181.30  5368.1 1182.22  5478.4 1182.50
  5489.1 1181.07  5508.5 1179.92  5528.6 1180.85  5538.6 1183.00  5593.7 1185.04
#Mann=3,-1,0
  4666.2    0.12       0  5105.5    0.07       0  5109.6    0.12       0
Bank Sta=5105.5,5109.6
Exp/Cntr=0.3,0.1

Type RM Length L Ch R = 1,23286,544,544,544
BEGIN DESCRIPTION:
BARNETT BRANCH 42.0
END DESCRIPTION:
XS GIS Cut Line= 3
      2847908.27     10179082.27      2847260.45     10178849.60
      2846854.40     10178749.23
#Sta/Elev= 30
  4552.4 1176.61  4624.3 1174.00  4710.9 1171.49  4803.1 1167.02  4828.5 1164.81
  4905.8 1154.95  4927.0 1149.43  4951.4 1144.99  4969.5 1139.40  4988.7 1136.82
  4989.0 1133.82  4992.6 1133.82  4992.8 1136.82  5001.4 1138.60  5007.6 1141.37
  5022.7 1143.91  5038.3 1145.22  5094.5 1154.08  5139.5 1159.22  5248.9 1164.41
  5266.2 1166.87  5290.3 1167.45  5307.4 1169.63  5373.2 1173.06  5462.0 1180.28
  5538.9 1184.04  5580.4 1187.53  5585.6 1188.93  5603.0 1189.72  5659.0 1193.55
#Mann=5,-1,0
  4552.4    0.05       0  4624.3    0.12       0  4988.7    0.07       0
  4992.8    0.12       0  5603.0    0.05       0
Bank Sta=4988.7,4992.8
Exp/Cntr=0.3,0.1

Type RM Length L Ch R = 1,22742,482,482,482
BEGIN DESCRIPTION:
BARNETT BRANCH 41.0
END DESCRIPTION:
XS GIS Cut Line= 3
      2847921.93     10178840.48      2847639.09     10178288.49
      2847334.44     10178097.51
#Sta/Elev= 30
  4558.6 1176.94  4605.7 1172.29  4611.8 1170.69  4650.1 1167.93  4738.9 1156.22
  4777.7 1149.80  4822.1 1146.19  4827.7 1146.61  4844.3 1142.93  4866.5 1140.21
  4888.7 1139.24  4926.4 1134.65  4960.9 1132.85  4977.5 1129.65  5003.2 1127.64
  5003.5 1124.64  5007.2 1124.64  5007.5 1127.64  5016.3 1132.66  5027.6 1141.07
  5044.1 1145.55  5050.0 1149.46  5072.5 1156.71  5149.5 1171.30  5155.1 1170.62
  5184.2 1174.26  5220.7 1177.07  5354.0 1182.59  5439.9 1183.87  5538.4 1180.99
#Mann=4,-1,0
  4558.6    0.12       0  5003.2    0.07       0  5007.5    0.12       0
  5354.0    0.05       0
Bank Sta=5003.2,5007.5
Exp/Cntr=0.3,0.1

Type RM Length L Ch R = 1,22260,352,352,352
BEGIN DESCRIPTION:
BARNETT BRANCH 40.0
END DESCRIPTION:
XS GIS Cut Line= 3
      2848442.00     10178954.55      2848026.85     10178288.49
      2847712.08     10178115.13
#Sta/Elev= 30
  4480.6 1182.94  4563.1 1178.79  4607.2 1177.04  4684.7 1172.59  4784.2 1168.02
  4805.4 1168.78  4820.8 1165.40  4826.6 1166.73  4842.0 1160.87  4847.9 1161.49
  4857.3 1156.93  4863.2 1158.04  4878.6 1149.31  4923.8 1131.66  4936.4 1127.16
  4970.8 1122.61  4971.1 1119.61  4974.8 1119.61  4975.1 1122.61  4994.2 1126.62
  5000.8 1124.56  5025.8 1123.45  5052.0 1125.96  5073.3 1131.36  5167.6 1143.40
  5269.4 1151.82  5312.9 1157.69  5475.7 1171.39  5613.1 1177.33  5624.8 1177.20
#Mann=9,-1,0
  4480.6    0.05       0  4563.1    0.12       0  4607.2    0.05       0
  4684.7    0.12       0  4923.8    0.05       0  4970.8    0.05       0
  4975.1    0.05       0  5025.8    0.12       0  5613.1    0.05       0
Bank Sta=4970.8,4975.1
Exp/Cntr=0.3,0.1

Type RM Length L Ch R = 1,21908,365,365,365
BEGIN DESCRIPTION:
BARNETT BRANCH 39.0
END DESCRIPTION:
XS GIS Cut Line= 3
      2848775.03     10178448.17      2848095.28     10178110.57
      2847830.68     10178033.02
#Sta/Elev= 30
  4451.1 1192.37  4453.6 1193.06  4470.4 1189.89  4509.0 1187.20  4600.7 1180.58
  4672.1 1174.45  4812.1 1157.13  4856.9 1148.54  4879.3 1142.24  4885.8 1138.89
  4901.7 1135.99  4930.5 1125.00  4957.9 1117.20  4991.3 1114.41  4997.5 1112.20
  5011.5 1110.83  5011.8 1107.83  5015.6 1107.83  5015.9 1110.83  5021.6 1116.41
  5030.6 1122.03  5036.1 1123.36  5042.1 1126.92  5058.6 1129.31  5109.1 1142.14
  5131.5 1146.19  5222.0 1159.44  5335.0 1166.42  5394.3 1169.97  5485.8 1173.02
#Mann=8,-1,0
  4451.1    0.12       0  4509.0    0.05       0  4600.7    0.12       0
  4957.9    0.05       0  5011.5    0.05       0  5015.9    0.05       0
  5021.6    0.12       0  5335.0    0.05       0
Bank Sta=5011.5,5015.9
Exp/Cntr=0.3,0.1

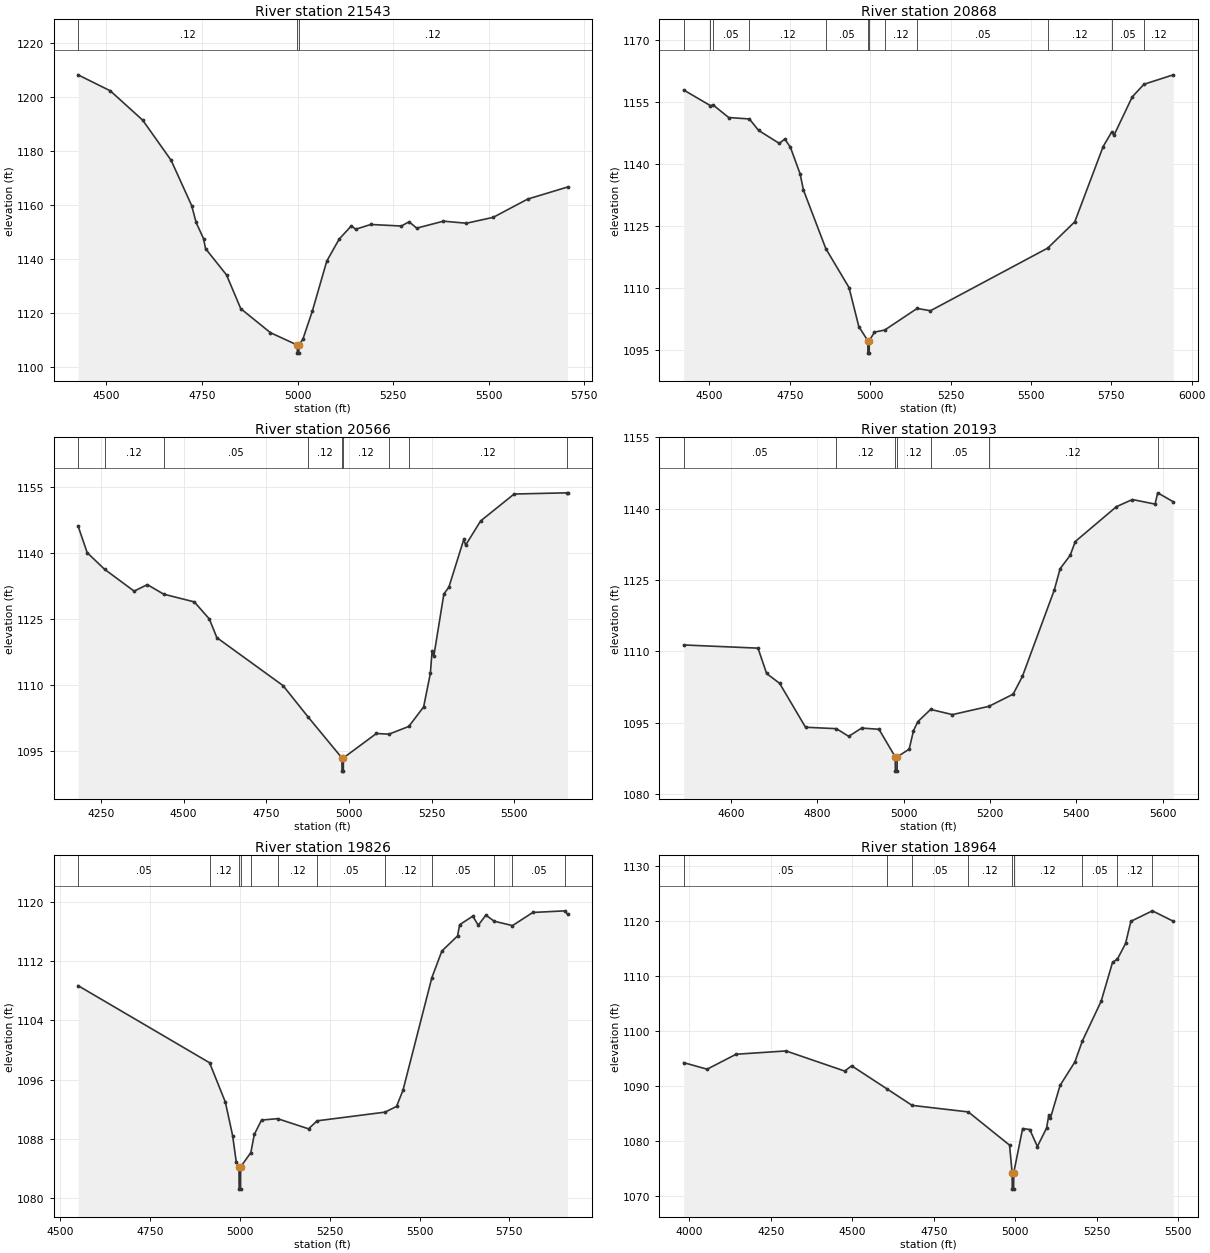
Type RM Length L Ch R = 1,21543,675,675,675
BEGIN DESCRIPTION:
BARNETT BRANCH 38.0
END DESCRIPTION:
XS GIS Cut Line= 3
      2849003.13     10178096.90      2848323.38     10177836.86
      2847771.35     10177827.73
#Sta/Elev= 30
  4426.0 1208.19  4510.4 1202.26  4595.2 1191.37  4669.3 1176.53  4723.1 1159.72
  4734.8 1153.45  4754.1 1147.48  4759.5 1143.75  4814.3 1134.00  4851.5 1121.49
  4929.1 1112.59  4999.2 1108.01  4999.5 1105.01  5003.3 1105.01  5003.6 1108.01
  5013.9 1110.18  5038.6 1120.59  5076.4 1139.13  5108.5 1147.23  5140.6 1152.20
  5152.0 1150.94  5191.5 1152.71  5271.5 1152.13  5291.5 1153.72  5311.5 1151.35
  5381.5 1153.93  5441.5 1153.17  5511.5 1155.35  5601.6 1162.12  5705.9 1166.59
#Mann=3,-1,0
  4426.0    0.12       0  4999.2    0.07       0  5003.6    0.12       0
Bank Sta=4999.2,5003.6
Exp/Cntr=0.3,0.1

Type RM Length L Ch R = 1,20868,302,302,302
BEGIN DESCRIPTION:
BARNETT BRANCH 37.0
END DESCRIPTION:
XS GIS Cut Line= 3
      2849021.36     10177453.67      2848775.01     10177262.06
      2847580.59     10177458.09
#Sta/Elev= 30
  4420.3 1157.94  4503.4 1154.15  4511.9 1154.31  4560.1 1151.28  4624.4 1150.93
  4653.3 1148.15  4717.5 1145.02  4734.6 1146.07  4752.0 1144.10  4782.4 1137.61
  4792.5 1133.77  4862.3 1119.54  4934.4 1110.13  4964.8 1100.70  4992.9 1097.26
  4993.2 1094.26  4997.1 1094.26  4997.4 1097.26  5013.6 1099.34  5045.5 1099.85
  5146.3 1105.08  5187.7 1104.52  5552.5 1119.69  5636.5 1126.04  5724.8 1144.26
  5750.8 1147.71  5759.0 1147.07  5815.2 1156.27  5851.6 1159.32  5942.8 1161.61
#Mann=12,-1,0
  4420.3    0.05       0  4503.4    0.12       0  4511.9    0.05       0
  4624.4    0.12       0  4862.3    0.05       0  4992.9    0.03       0
  4997.4    0.05       0  5045.5    0.12       0  5146.3    0.05       0
  5552.5    0.12       0  5750.8    0.05       0  5851.6    0.12       0
Bank Sta=4992.9,4997.4
Exp/Cntr=0.3,0.1

Type RM Length L Ch R = 1,20566,373,373,373
BEGIN DESCRIPTION:
BARNETT BRANCH 36.0
END DESCRIPTION:
XS GIS Cut Line= 3
      2849117.16     10177239.25      2848606.22     10176997.47
      2847709.08     10177179.63
#Sta/Elev= 30
  4180.5 1146.10  4208.2 1140.01  4260.7 1136.25  4350.2 1131.28  4390.2 1132.76
  4439.6 1130.59  4532.2 1128.84  4577.7 1124.96  4600.5 1120.72  4800.8 1109.83
  4876.1 1102.75  4978.7 1093.43  4979.0 1090.43  4982.9 1090.43  4983.2 1093.43
  5083.0 1098.97  5121.1 1098.82  5181.0 1100.57  5225.9 1105.01  5246.3 1112.64
  5251.5 1117.75  5256.6 1116.49  5287.1 1130.64  5302.1 1132.15  5347.6 1143.08
  5352.8 1141.70  5398.3 1147.21  5499.6 1153.32  5660.2 1153.59  5661.2 1153.56
#Mann=9,-1,0
  4180.5    0.05       0  4260.7    0.12       0  4439.6    0.05       0
  4876.1    0.12       0  4978.7    0.07       0  4983.2    0.12       0
  5121.1    0.05       0  5181.0    0.12       0  5660.2    0.05       0
Bank Sta=4978.7,4983.2
Exp/Cntr=0.3,0.1

Type RM Length L Ch R = 1,20193,367,367,367
BEGIN DESCRIPTION:
BARNETT BRANCH 35.0
END DESCRIPTION:
XS GIS Cut Line= 3
      2848747.61     10176673.57      2848086.16     10176705.50
      2847680.38     10176947.15
#Sta/Elev= 30
  4490.1 1111.35  4662.2 1110.68  4682.2 1105.35  4712.3 1103.28  4772.4 1094.04
  4844.0 1093.74  4872.5 1092.12  4902.5 1093.87  4942.6 1093.61  4980.3 1087.81
  4980.6 1084.81  4984.5 1084.81  4984.8 1087.81  5012.6 1089.43  5022.6 1093.33
  5032.7 1095.23  5062.3 1097.79  5112.8 1096.70  5197.4 1098.44  5253.5 1101.00
  5274.9 1104.72  5348.9 1122.91  5362.4 1127.39  5385.7 1130.20  5397.5 1133.11
  5492.9 1140.44  5529.9 1141.94  5582.5 1140.98  5588.5 1143.35  5624.6 1141.47
#Mann=7,-1,0
  4490.1    0.05       0  4844.0    0.12       0  4980.3    0.07       0
  4984.8    0.12       0  5062.3    0.05       0  5197.4    0.12       0
  5588.5    0.05       0
Bank Sta=4980.3,4984.8
Exp/Cntr=0.3,0.1

Type RM Length L Ch R = 1,19826,862,862,862
BEGIN DESCRIPTION:
BARNETT BRANCH 34.0
END DESCRIPTION:
XS GIS Cut Line= 4
      2848688.33     10176513.90      2848519.54     10176322.30
      2847894.56     10176395.29      2847489.62     10176650.09
#Sta/Elev= 30
  4549.0 1108.69  4915.2 1098.29  4959.2 1092.99  4979.4 1088.48  4989.4 1084.97
  4997.2 1084.25  4997.6 1081.25  5001.5 1081.25  5001.8 1084.25  5030.2 1086.18
  5039.8 1088.62  5059.9 1090.56  5104.6 1090.75  5190.8 1089.38  5214.9 1090.46
  5403.9 1091.63  5435.9 1092.40  5453.8 1094.58  5534.2 1109.76  5562.2 1113.36
  5605.7 1115.38  5611.6 1116.90  5648.1 1118.05  5663.4 1116.83  5684.6 1118.19
  5707.7 1117.37  5758.7 1116.78  5815.3 1118.55  5905.6 1118.77  5912.0 1118.29
#Mann=12,-1,0
  4549.0    0.05       0  4915.2    0.12       0  4997.2    0.07       0
  5001.8    0.12       0  5030.2    0.05       0  5104.6    0.12       0
  5214.9    0.05       0  5403.9    0.12       0  5534.2    0.05       0
  5707.7    0.12       0  5758.7    0.05       0  5905.6    0.12       0
Bank Sta=4997.2,5001.8
Exp/Cntr=0.3,0.1

Type RM Length L Ch R = 1,18964,366,366,366
BEGIN DESCRIPTION:
BARNETT BRANCH 33.0
END DESCRIPTION:
XS GIS Cut Line= 3
      2848765.90     10176263.01      2848255.68     10175953.11
      2847379.85     10175720.34
#Sta/Elev= 30
  3982.3 1094.26  4054.1 1093.07  4143.2 1095.79  4296.3 1096.39  4476.6 1092.73
  4497.9 1093.69  4607.2 1089.46  4683.6 1086.49  4856.2 1085.30  4982.8 1079.26
  4990.7 1074.26  4991.1 1071.26  4995.3 1071.26  4995.7 1074.26  5023.0 1082.28
  5044.9 1082.10  5068.3 1079.01  5096.6 1082.39  5103.3 1084.72  5108.5 1084.21
  5138.0 1090.13  5183.6 1094.40  5206.1 1098.17  5264.0 1105.41  5299.0 1112.49
  5314.2 1113.10  5339.1 1115.95  5355.3 1119.96  5421.4 1121.87  5485.5 1119.98
#Mann=9,-1,0
  3982.3    0.05       0  4607.2    0.12       0  4683.6    0.05       0
  4856.2    0.12       0  4990.7    0.07       0  4995.7    0.12       0
  5206.1    0.05       0  5314.2    0.12       0  5421.4    0.05       0
Bank Sta=4990.7,4995.7
Exp/Cntr=0.3,0.1

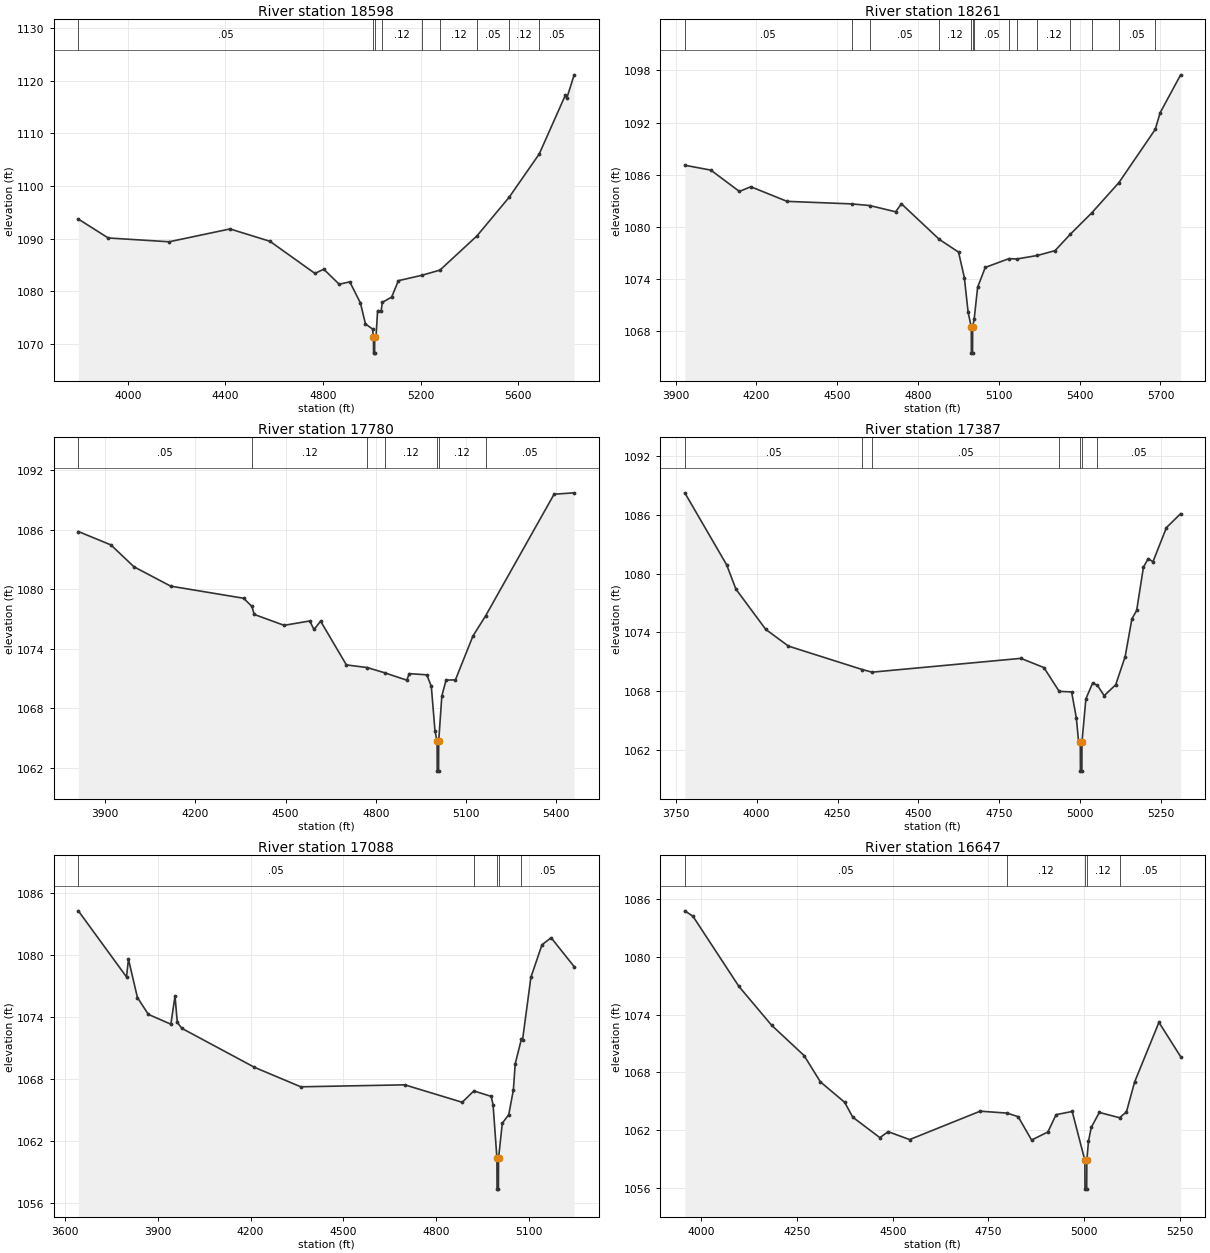
Type RM Length L Ch R = 1,18598,337,337,337
BEGIN DESCRIPTION:
BARNETT BRANCH 32.0
END DESCRIPTION:
XS GIS Cut Line= 3
      2849089.78     10176381.61      2847976.67     10175514.85
      2847360.77     10175423.60
#Sta/Elev= 30
  3796.7 1093.71  3919.3 1090.11  4169.4 1089.39  4418.7 1091.83  4582.5 1089.48
  4767.1 1083.37  4803.2 1084.17  4866.6 1081.31  4910.0 1081.77  4953.5 1077.75
  4974.3 1073.76  5003.2 1072.80  5007.1 1071.21  5007.5 1068.21  5011.7 1068.21
  5012.1 1071.21  5017.7 1071.47  5024.0 1076.30  5038.5 1076.16  5043.3 1077.86
  5081.9 1078.88  5109.1 1081.99  5204.3 1083.00  5279.7 1084.00  5431.5 1090.51
  5563.9 1097.88  5686.9 1106.09  5794.5 1117.32  5799.6 1116.65  5830.1 1121.14
#Mann=9,-1,0
  3796.7    0.05       0  5007.1    0.05       0  5012.1    0.05       0
  5043.3    0.12       0  5204.3    0.05       0  5279.7    0.12       0
  5431.5    0.05       0  5563.9    0.12       0  5686.9    0.05       0
Bank Sta=5007.1,5012.1
Exp/Cntr=0.3,0.1

Type RM Length L Ch R = 1,18261,481,481,481
BEGIN DESCRIPTION:
BARNETT BRANCH 31.0
END DESCRIPTION:
XS GIS Cut Line= 3
      2849139.99     10176135.29      2848241.26     10175305.00
      2847643.63     10175149.89
#Sta/Elev= 30
  3933.9 1087.10  4030.6 1086.54  4136.6 1084.09  4179.1 1084.63  4313.5 1082.95
  4552.9 1082.66  4620.7 1082.47  4716.7 1081.75  4738.2 1082.67  4879.3 1078.57
  4950.3 1077.12  4971.8 1074.20  4986.0 1070.18  4997.7 1068.51  4998.0 1065.51
  5002.3 1065.51  5002.7 1068.51  5008.5 1069.46  5021.2 1073.08  5049.5 1075.36
  5137.8 1076.37  5166.5 1076.33  5243.0 1076.73  5308.7 1077.29  5365.5 1079.18
  5444.7 1081.62  5545.6 1085.10  5680.7 1091.22  5698.8 1093.13  5774.9 1097.49
#Mann=14,-1,0
  3933.9    0.05       0  4552.9    0.12       0  4620.7    0.05       0
  4879.3    0.12       0  4997.7    0.07       0  5002.7    0.12       0
  5008.5    0.05       0  5137.8    0.12       0  5166.5    0.05       0
  5243.0    0.12       0  5365.5    0.05       0  5444.7    0.12       0
  5545.6    0.05       0  5680.7    0.12       0
Bank Sta=4997.7,5002.7
Exp/Cntr=0.3,0.1

Type RM Length L Ch R = 1,17780,393,393,393
BEGIN DESCRIPTION:
BARNETT BRANCH 30.0
END DESCRIPTION:
XS GIS Cut Line= 3
      2849390.87     10175888.92      2848779.57     10175104.27
      2848218.46     10174766.69
#Sta/Elev= 30
  3810.5 1085.82  3918.8 1084.47  3995.7 1082.26  4117.9 1080.31  4360.3 1079.09
  4387.9 1078.27  4395.6 1077.46  4495.1 1076.36  4580.2 1076.80  4594.6 1075.94
  4616.5 1076.78  4702.3 1072.37  4772.0 1072.10  4829.1 1071.58  4903.1 1070.83
  4911.5 1071.49  4969.8 1071.37  4984.8 1070.21  4997.0 1065.72  5004.1 1064.66
  5004.5 1061.66  5008.9 1061.66  5009.3 1064.66  5019.8 1069.24  5033.9 1070.84
  5065.0 1070.86  5123.2 1075.28  5165.1 1077.30  5393.2 1089.58  5460.0 1089.72
#Mann=7,-1,0
  3810.5    0.05       0  4387.9    0.12       0  4772.0    0.05       0
  4829.1    0.12       0  5004.1    0.07       0  5009.3    0.12       0
  5165.1    0.05       0
Bank Sta=5004.1,5009.3
Exp/Cntr=0.3,0.1

Type RM Length L Ch R = 1,17387,299,299,299
BEGIN DESCRIPTION:
BARNETT BRANCH 29.0
END DESCRIPTION:
XS GIS Cut Line= 3
      2849769.53     10175441.88      2849098.90     10174871.62
      2848570.17     10174488.74
#Sta/Elev= 30
  3777.8 1088.26  3907.3 1080.90  3935.9 1078.42  4028.1 1074.31  4098.4 1072.60
  4326.3 1070.21  4356.9 1069.94  4817.0 1071.35  4888.1 1070.41  4935.4 1067.98
  4973.9 1067.92  4988.6 1065.23  4995.4 1062.84  5000.7 1062.83  5001.1 1059.83
  5005.5 1059.83  5005.9 1062.83  5018.0 1067.22  5038.9 1068.83  5053.6 1068.59
  5074.5 1067.54  5110.1 1068.65  5139.4 1071.53  5160.3 1075.39  5175.0 1076.25
  5195.9 1080.66  5210.6 1081.54  5225.3 1081.22  5267.1 1084.71  5310.9 1086.13
#Mann=7,-1,0
  3777.8    0.05       0  4326.3    0.12       0  4356.9    0.05       0
  4935.4    0.12       0  5000.7    0.07       0  5005.9    0.12       0
  5053.6    0.05       0
Bank Sta=5000.7,5005.9
Exp/Cntr=0.3,0.1

Type RM Length L Ch R = 1,17088,441,441,441
BEGIN DESCRIPTION:
BARNETT BRANCH 28.0
END DESCRIPTION:
XS GIS Cut Line= 3
      2850034.06     10175222.86      2849126.27     10174529.47
      2848749.14     10174265.93
#Sta/Elev= 30
  3643.3 1084.30  3799.0 1077.89  3805.3 1079.61  3834.3 1075.89  3869.7 1074.26
  3942.3 1073.31  3955.8 1076.04  3963.1 1073.49  3977.7 1072.91  4212.5 1069.13
  4362.2 1067.24  4698.3 1067.43  4883.9 1065.74  4921.5 1066.84  4977.7 1066.31
  4983.8 1065.46  4996.1 1060.32  4996.5 1057.32  5000.9 1057.32  5001.3 1060.32
  5013.5 1063.71  5034.4 1064.55  5049.2 1066.93  5055.3 1069.48  5074.9 1071.83
  5078.9 1071.78  5105.9 1077.85  5141.7 1081.01  5171.3 1081.69  5245.7 1078.89
#Mann=5,-1,0
  3643.3    0.05       0  4921.5    0.12       0  4996.1    0.07       0
  5001.3    0.12       0  5074.9    0.05       0
Bank Sta=4996.1,5001.3
Exp/Cntr=0.3,0.1

Type RM Length L Ch R = 1,16647,1629,1629,1629
BEGIN DESCRIPTION:
BARNETT BRANCH 27.0
END DESCRIPTION:
XS GIS Cut Line= 3
      2850005.65     10174803.08      2849399.99     10174242.07
      2849060.58     10173918.20
#Sta/Elev= 30
  3957.1 1084.78  3978.3 1084.22  4098.5 1076.92  4183.6 1072.90  4268.6 1069.74
  4311.1 1067.01  4374.6 1064.88  4395.6 1063.34  4466.5 1061.21  4488.0 1061.83
  4544.2 1061.01  4728.4 1063.96  4798.5 1063.76  4827.5 1063.39  4862.7 1060.96
  4905.2 1061.80  4926.6 1063.60  4968.7 1063.93  5001.7 1058.86  5002.1 1055.86
  5006.5 1055.86  5006.9 1058.86  5011.2 1060.83  5018.4 1062.27  5039.5 1063.83
  5092.3 1063.28  5110.3 1063.88  5131.7 1067.00  5195.2 1073.19  5251.8 1069.63
#Mann=5,-1,0
  3957.1    0.05       0  4798.5    0.12       0  5001.7    0.07       0
  5006.9    0.12       0  5092.3    0.05       0
Bank Sta=5001.7,5006.9
Exp/Cntr=0.3,0.1

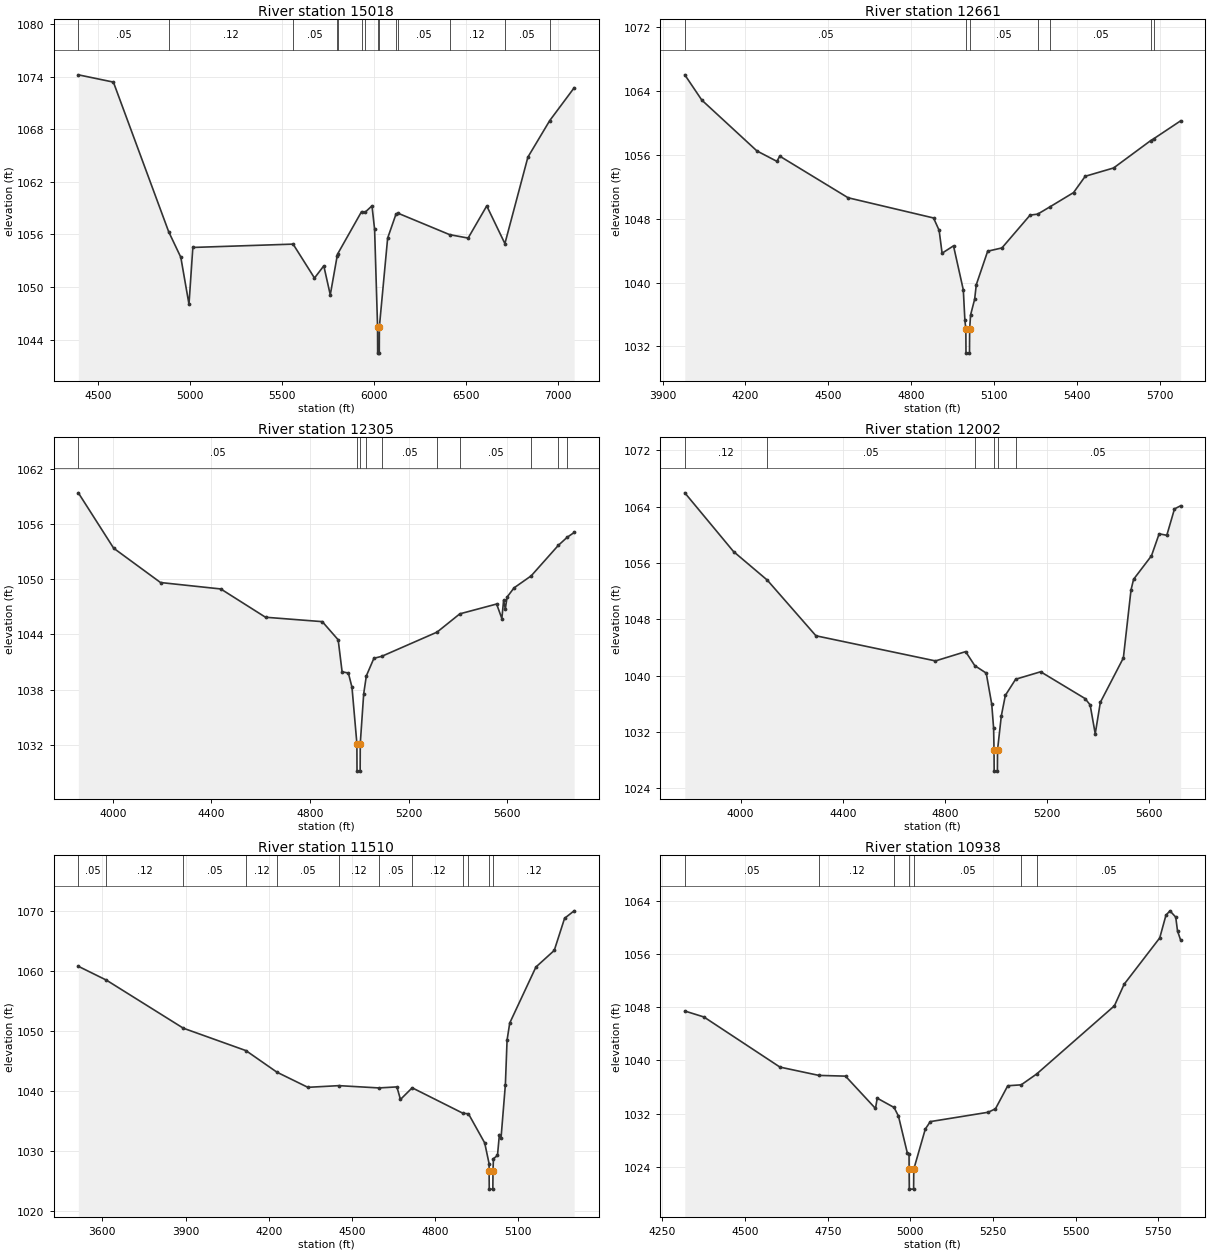
Type RM Length L Ch R = 1,15018,2357,2357,2357
BEGIN DESCRIPTION:
BARNETT BRANCH 26.0
END DESCRIPTION:
XS GIS Cut Line= 4
      2850570.73     10174204.51      2849471.81     10173433.71
      2849174.93     10173152.46      2848883.50     10172257.35
#Sta/Elev= 30
  4393.8 1074.21  4584.2 1073.38  4884.5 1056.30  4950.3 1053.39  4994.7 1048.03
  5015.6 1054.51  5560.1 1054.89  5676.3 1051.02  5726.8 1052.41  5762.0 1049.10
  5799.6 1053.56  5802.6 1053.79  5931.6 1058.59  5952.3 1058.55  5988.5 1059.26
  6002.7 1056.58  6018.8 1045.45  6019.3 1042.45  6028.1 1042.45  6028.6 1045.45
  6073.5 1055.57  6119.1 1058.33  6131.8 1058.40  6410.4 1055.97  6510.6 1055.58
  6611.7 1059.25  6710.3 1054.95  6835.2 1064.82  6953.5 1068.98  7086.4 1072.73
#Mann=14,-1,0
  4393.8    0.05       0  4884.5    0.12       0  5560.1    0.05       0
  5799.6    0.12       0  5802.6    0.05       0  5931.6    0.12       0
  5952.3    0.05       0  6018.8    0.07       0  6028.6    0.05       0
  6119.1    0.12       0  6131.8    0.05       0  6410.4    0.12       0
  6710.3    0.05       0  6953.5    0.12       0
Bank Sta=6018.8,6028.6
Exp/Cntr=0.3,0.1

Type RM Length L Ch R = 1,12661,356,356,356
BEGIN DESCRIPTION:
BARNETT BRANCH 25.0
END DESCRIPTION:
XS GIS Cut Line= 3
      2850575.98     10173876.43      2850258.27     10172610.79
      2849992.62     10172199.30
#Sta/Elev= 30
  3980.4 1066.01  4041.9 1062.85  4241.6 1056.48  4313.8 1055.18  4324.1 1055.83
  4571.5 1050.62  4880.8 1048.09  4901.0 1046.54  4911.7 1043.68  4953.0 1044.60
  4988.5 1039.09  4994.2 1035.31  4997.7 1034.17  4998.2 1031.17  5010.9 1031.17
  5011.4 1034.17  5014.8 1035.94  5029.6 1037.93  5035.5 1039.74  5076.7 1043.93
  5128.3 1044.34  5230.3 1048.45  5257.6 1048.57  5302.9 1049.50  5387.6 1051.27
  5429.8 1053.31  5532.5 1054.35  5666.9 1057.78  5677.8 1058.01  5775.1 1060.25
#Mann=7,-1,0
  3980.4    0.05       0  4997.7    0.03       0  5011.4    0.05       0
  5257.6    0.12       0  5302.9    0.05       0  5666.9    0.12       0
  5677.8    0.05       0
Bank Sta=4997.7,5011.4
Exp/Cntr=0.3,0.1

Type RM Length L Ch R = 1,12305,303,303,303
BEGIN DESCRIPTION:
BARNETT BRANCH 24.0
END DESCRIPTION:
XS GIS Cut Line= 3
      2850956.17     10173881.58      2850617.64     10172610.79
      2850122.83     10172121.19
#Sta/Elev= 30
  3860.0 1059.42  4003.3 1053.39  4193.4 1049.65  4437.9 1048.95  4619.2 1045.87
  4849.6 1045.39  4914.0 1043.41  4929.9 1039.93  4955.4 1039.79  4970.0 1038.24
  4989.9 1032.11  4990.4 1029.11  5003.1 1029.11  5003.6 1032.11  5017.5 1037.53
  5028.3 1039.49  5058.9 1041.40  5090.4 1041.61  5315.1 1044.25  5407.4 1046.24
  5556.7 1047.31  5577.9 1045.73  5585.0 1047.70  5592.0 1046.79  5599.2 1048.07
  5627.4 1049.07  5697.0 1050.38  5807.0 1053.70  5843.0 1054.58  5871.2 1055.10
#Mann=10,-1,0
  3860.0    0.05       0  4989.9    0.05       0  5003.6    0.05       0
  5028.3    0.12       0  5090.4    0.05       0  5315.1    0.12       0
  5407.4    0.05       0  5697.0    0.12       0  5807.0    0.05       0
  5843.0    0.12       0
Bank Sta=4989.9,5003.6
Exp/Cntr=0.3,0.1

Type RM Length L Ch R = 1,12002,492,492,492
BEGIN DESCRIPTION:
BARNETT BRANCH 23.0
END DESCRIPTION:
XS GIS Cut Line= 3
      2851555.68     10173753.10      2850851.80     10172519.98
      2850830.09     10171999.10
#Sta/Elev= 30
  3781.5 1065.97  3972.3 1057.63  4104.3 1053.58  4294.9 1045.67  4762.9 1042.10
  4881.0 1043.42  4916.8 1041.43  4961.6 1040.37  4983.2 1035.96  4990.5 1032.56
  4992.2 1029.45  4992.7 1026.45  5005.4 1026.45  5005.9 1029.45  5020.7 1034.29
  5036.5 1037.21  5076.8 1039.50  5174.7 1040.56  5348.4 1036.76  5368.4 1035.86
  5388.4 1031.75  5408.4 1036.22  5498.5 1042.52  5528.5 1052.18  5538.5 1053.69
  5608.6 1057.03  5638.6 1060.15  5668.6 1059.94  5698.7 1063.69  5722.7 1064.13
#Mann=6,-1,0
  3781.5    0.12       0  4104.3    0.05       0  4916.8    0.12       0
  4992.2    0.07       0  5005.9    0.12       0  5076.8    0.05       0
Bank Sta=4992.2,5005.9
Exp/Cntr=0.3,0.1

Type RM Length L Ch R = 1,11510,572,572,572
BEGIN DESCRIPTION:
BARNETT BRANCH 22.0
END DESCRIPTION:
XS GIS Cut Line= 3
      2851767.61     10173626.79      2851159.96     10172385.43
      2850955.94     10172033.84
#Sta/Elev= 30
  3513.3 1060.73  3614.5 1058.43  3892.0 1050.43  4117.9 1046.70  4229.7 1043.11
  4341.3 1040.59  4453.2 1040.87  4597.4 1040.49  4662.5 1040.66  4675.3 1038.57
  4717.6 1040.51  4900.5 1036.28  4920.7 1036.18  4979.2 1031.34  4995.0 1027.90
  4995.1 1026.65  4995.6 1023.65  5008.6 1023.65  5009.1 1026.65  5010.7 1028.72
  5025.3 1029.25  5032.2 1032.73  5038.0 1032.09  5053.8 1041.05  5059.9 1048.45
  5069.5 1051.29  5164.0 1060.61  5230.1 1063.37  5267.4 1068.72  5301.9 1069.96
#Mann=12,-1,0
  3513.3    0.05       0  3614.5    0.12       0  3892.0    0.05       0
  4117.9    0.12       0  4229.7    0.05       0  4453.2    0.12       0
  4597.4    0.05       0  4717.6    0.12       0  4900.5    0.05       0
  4920.7    0.12       0  4995.1    0.07       0  5009.1    0.12       0
Bank Sta=4995.1,5009.1
Exp/Cntr=0.3,0.1

Type RM Length L Ch R = 1,10938,559,559,559
BEGIN DESCRIPTION:
BARNETT BRANCH 21.0
END DESCRIPTION:
XS GIS Cut Line= 3
      2851867.44     10173006.14      2851607.01     10172194.46
      2851005.66     10171953.10
#Sta/Elev= 30
  4317.5 1047.44  4375.4 1046.54  4605.5 1038.99  4723.3 1037.74  4803.8 1037.63
  4894.5 1032.76  4899.8 1034.31  4950.8 1032.91  4964.0 1031.62  4990.9 1026.05
  4996.1 1025.91  4996.3 1023.61  4996.8 1020.61  5009.9 1020.61  5010.4 1023.61
  5045.3 1029.66  5060.4 1030.78  5235.6 1032.19  5257.6 1032.71  5294.8 1036.18
  5335.5 1036.32  5382.2 1037.95  5617.5 1048.22  5647.1 1051.48  5754.7 1058.45
  5773.5 1061.87  5785.6 1062.53  5803.1 1061.58  5808.5 1059.50  5817.9 1058.13
#Mann=7,-1,0
  4317.5    0.05       0  4723.3    0.12       0  4950.8    0.05       0
  4996.3    0.05       0  5010.4    0.05       0  5335.5    0.12       0
  5382.2    0.05       0
Bank Sta=4996.3,5010.4
Exp/Cntr=0.3,0.1

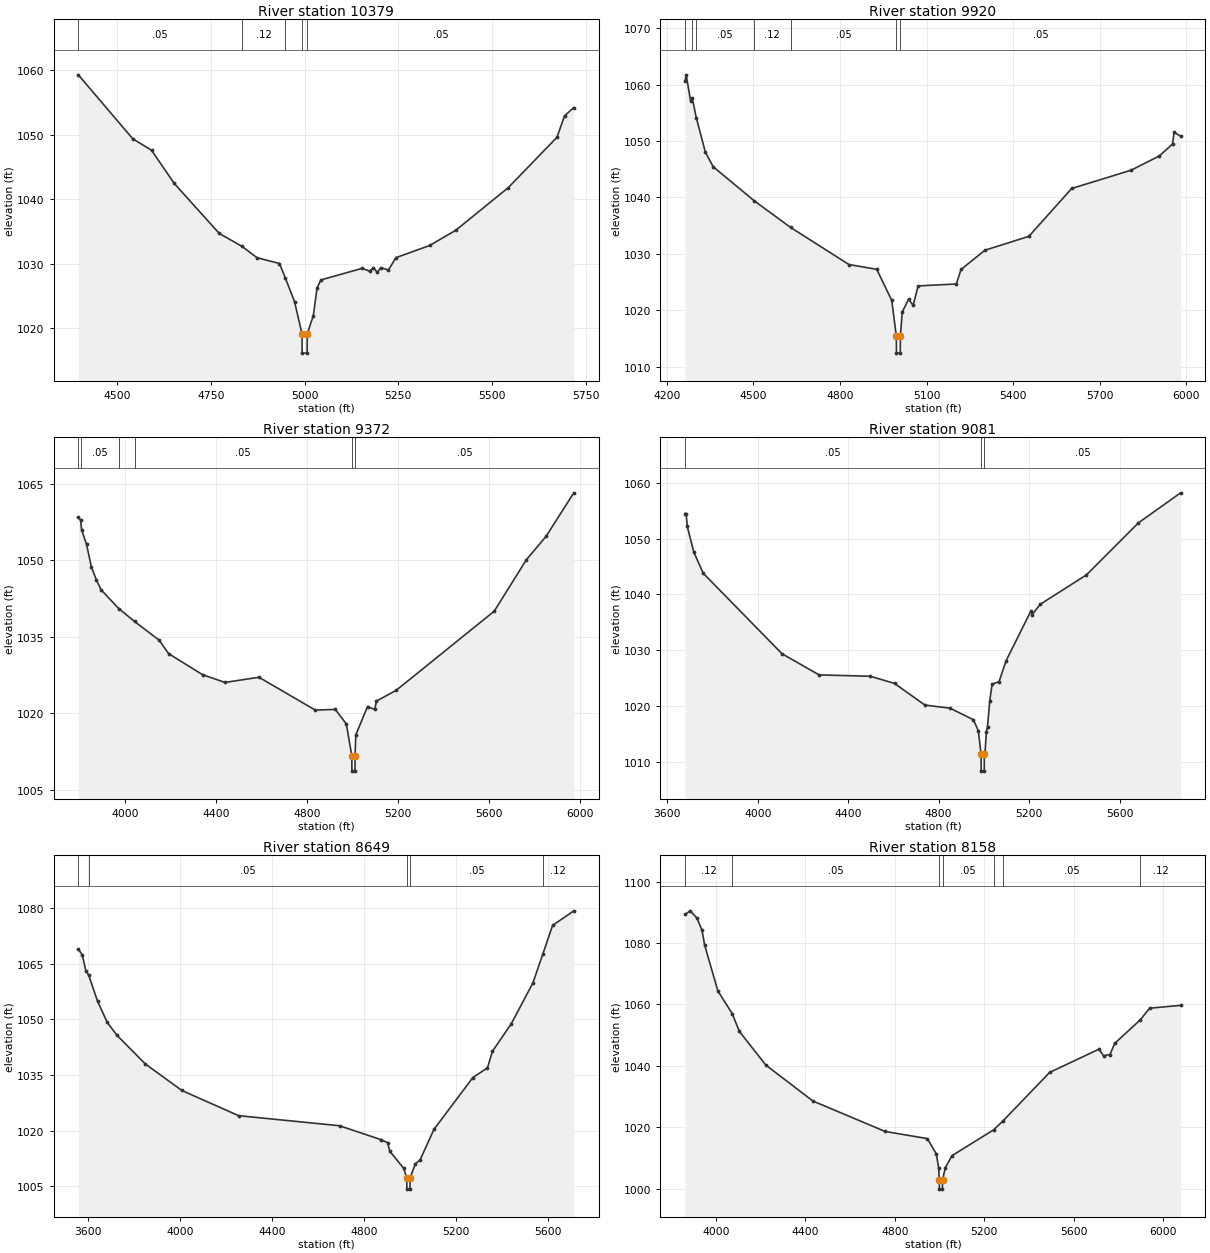
Type RM Length L Ch R = 1,10379,459,459,459
BEGIN DESCRIPTION:
BARNETT BRANCH 20.0
END DESCRIPTION:
XS GIS Cut Line= 3
      2852440.38     10171881.96      2851693.81     10171951.41
      2851120.85     10171938.39
#Sta/Elev= 30
  4395.8 1059.31  4541.1 1049.40  4591.3 1047.62  4651.6 1042.50  4772.1 1034.73
  4833.1 1032.72  4872.5 1030.98  4932.8 1030.07  4948.0 1027.90  4973.0 1024.17
  4993.0 1019.18  4993.5 1016.18  5006.6 1016.18  5007.1 1019.18  5023.2 1021.97
  5033.2 1026.27  5043.3 1027.52  5153.7 1029.32  5173.7 1028.87  5183.7 1029.43
  5193.7 1028.69  5203.7 1029.43  5223.7 1029.05  5243.7 1030.97  5333.8 1032.86
  5403.8 1035.23  5543.8 1041.83  5673.9 1049.64  5693.9 1052.95  5718.7 1054.24
#Mann=5,-1,0
  4395.8    0.05       0  4833.1    0.12       0  4948.0    0.05       0
  4993.0    0.05       0  5007.1    0.05       0
Bank Sta=4993,5007.1
Exp/Cntr=0.3,0.1

Type RM Length L Ch R = 1,9920,548,548,548
BEGIN DESCRIPTION:
Mapping XS 2aa7edd6
END DESCRIPTION:
XS GIS Cut Line= 3
      2852375.24     10171769.12      2851871.76     10171439.25
      2850860.62     10171907.94
#Sta/Elev= 30
  4263.5 1060.69  4267.1 1061.72  4282.2 1057.14  4287.9 1057.67  4302.0 1054.13
  4333.5 1048.02  4360.6 1045.44  4502.3 1039.42  4628.5 1034.69  4830.9 1028.11
  4927.2 1027.26  4979.2 1021.74  4995.1 1015.41  4995.6 1012.41  5008.7 1012.41
  5009.2 1015.41  5015.4 1019.67  5037.4 1021.96  5053.5 1020.88  5070.5 1024.32
  5202.8 1024.66  5219.3 1027.24  5302.0 1030.64  5454.0 1033.10  5602.5 1041.58
  5808.7 1044.83  5905.8 1047.34  5951.7 1049.45  5957.2 1051.53  5979.9 1050.85
#Mann=7,-1,0
  4263.5    0.05       0  4287.9    0.12       0  4302.0    0.05       0
  4502.3    0.12       0  4628.5    0.05       0  4995.1    0.03       0
  5009.2    0.05       0
Bank Sta=4995.1,5009.2
Exp/Cntr=0.3,0.1

Type RM Length L Ch R = 1,9372,291,291,291
BEGIN DESCRIPTION:
BARNETT BRANCH 19.0
END DESCRIPTION:
XS GIS Cut Line= 4
      2852388.28     10171721.40      2851667.77     10170957.48
      2851311.87     10171057.31      2850556.71     10171022.59
#Sta/Elev= 30
  3796.1 1058.48  3806.0 1057.84  3810.8 1055.93  3832.2 1053.12  3853.3 1048.72
  3874.7 1046.23  3895.7 1044.24  3973.7 1040.54  4043.0 1038.01  4150.6 1034.37
  4192.7 1031.71  4341.6 1027.59  4440.3 1026.07  4589.2 1027.09  4836.8 1020.65
  4924.4 1020.79  4973.0 1017.94  4997.0 1011.70  4997.5 1008.70  5010.8 1008.70
  5011.3 1011.70  5014.5 1015.79  5066.0 1021.35  5097.6 1020.79  5105.3 1022.43
  5191.1 1024.50  5622.5 1040.03  5762.6 1050.05  5849.6 1054.66  5971.8 1063.21
#Mann=6,-1,0
  3796.1    0.12       0  3806.0    0.05       0  3973.7    0.12       0
  4043.0    0.05       0  4997.0    0.05       0  5011.3    0.05       0
Bank Sta=4997,5011.3
Exp/Cntr=0.3,0.1

Type RM Length L Ch R = 1,9081,432,432,432
BEGIN DESCRIPTION:
BARNETT BRANCH 18.0
END DESCRIPTION:
XS GIS Cut Line= 4
      2852396.95     10171664.97      2851658.18     10170759.22
      2851251.10     10170653.66      2850649.21     10170640.67
#Sta/Elev= 30
  3678.9 1054.47  3683.3 1054.47  3688.3 1052.19  3717.0 1047.59  3758.7 1043.79
  4107.1 1029.37  4271.3 1025.58  4498.2 1025.33  4605.2 1024.04  4739.5 1020.17
  4849.9 1019.62  4953.6 1017.56  4975.6 1015.56  4987.8 1011.34  4988.3 1008.34
  5001.6 1008.34  5002.1 1011.34  5005.3 1011.69  5011.0 1015.29  5016.1 1016.30
  5025.9 1020.83  5036.3 1023.91  5067.3 1024.38  5098.2 1028.09  5208.7 1037.08
  5213.9 1036.39  5249.3 1038.22  5453.7 1043.49  5683.8 1052.82  5870.3 1058.19
#Mann=3,-1,0
  3678.9    0.05       0  4987.8    0.05       0  5002.1    0.05       0
Bank Sta=4987.8,5002.1
Exp/Cntr=0.3,0.1

Type RM Length L Ch R = 1,8649,491,491,491
BEGIN DESCRIPTION:
Mapping XS 8b22135b
END DESCRIPTION:
XS GIS Cut Line= 4
      2852509.79     10171673.63      2851841.38     10170671.03
      2851793.64     10170297.76      2851490.26     10169812.36
#Sta/Elev= 30
  3557.6 1068.89  3575.1 1067.33  3590.2 1063.11  3602.9 1061.85  3641.2 1054.88
  3683.3 1049.16  3726.5 1045.64  3848.6 1037.99  4007.8 1030.83  4254.2 1024.05
  4692.9 1021.34  4871.4 1017.63  4901.6 1016.79  4911.7 1014.46  4972.2 1009.83
  4985.2 1007.27  4985.7 1004.27  4999.1 1004.27  4999.6 1007.27  5022.6 1011.10
  5042.8 1012.09  5103.2 1020.34  5272.4 1034.30  5336.0 1036.92  5357.3 1041.36
  5439.2 1048.77  5533.5 1059.78  5576.2 1067.49  5619.1 1075.28  5711.3 1079.21
#Mann=5,-1,0
  3557.6    0.12       0  3602.9    0.05       0  4985.2    0.03       0
  4999.6    0.05       0  5576.2    0.12       0
Bank Sta=4985.2,4999.6
Exp/Cntr=0.3,0.1

Type RM Length L Ch R = 1,8158,358,358,358
BEGIN DESCRIPTION:
BARNETT BRANCH 17.0
END DESCRIPTION:
XS GIS Cut Line= 4
      2852731.16     10171608.56      2852253.71     10170775.19
      2852284.09     10170458.35      2851690.08     10169734.27
#Sta/Elev= 30
  3862.8 1089.31  3885.1 1090.49  3915.2 1088.18  3938.2 1084.16  3949.9 1079.36
  4008.9 1064.45  4072.9 1057.06  4105.2 1051.24  4223.2 1040.30  4433.8 1028.58
  4756.5 1018.67  4945.9 1016.34  4986.1 1011.28  4996.1 1006.77  4998.9 1002.89
  4999.4  999.89  5012.9  999.89  5013.4 1002.89  5026.3 1006.90  5056.4 1010.81
  5242.8 1019.23  5285.5 1022.22  5492.4 1037.88  5712.7 1045.45  5733.6 1043.28
  5762.3 1043.71  5783.1 1047.32  5897.4 1054.98  5939.5 1058.80  6078.1 1059.71
#Mann=7,-1,0
  3862.8    0.12       0  4072.9    0.05       0  4998.9    0.05       0
  5013.4    0.05       0  5242.8    0.12       0  5285.5    0.05       0
  5897.4    0.12       0
Bank Sta=4998.9,5013.4
Exp/Cntr=0.3,0.1