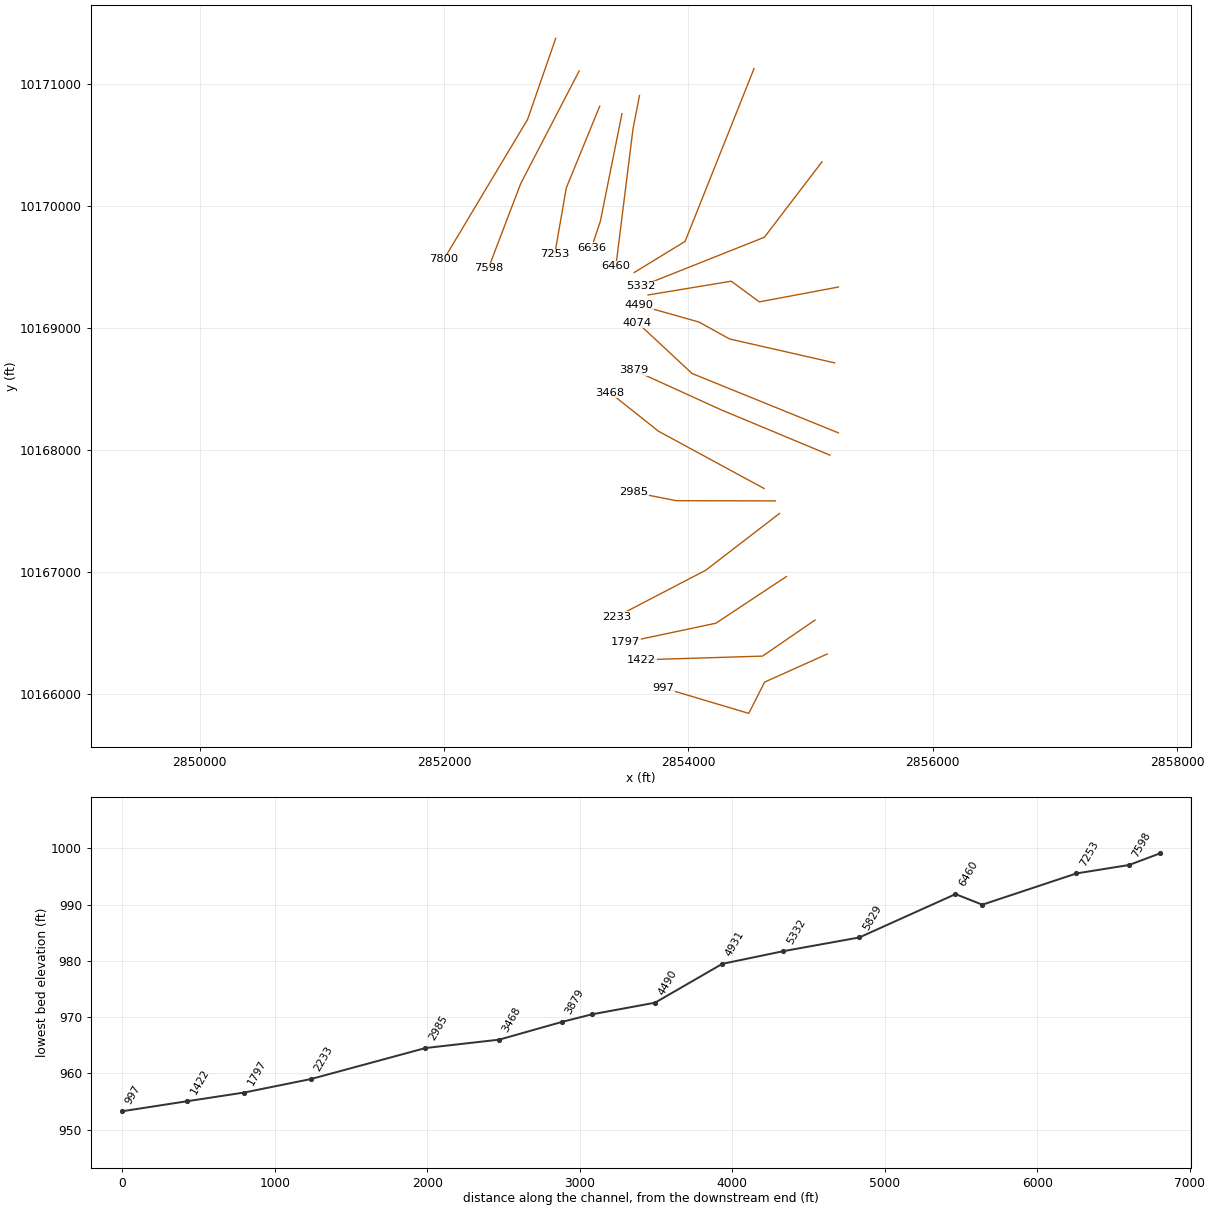
HEC-RAS study BARNETT BRANCH.prj: BARNETT BRANCH Base Level Engineering

--- BARNETT BRANCH.g01 (geometry) --- (continued)

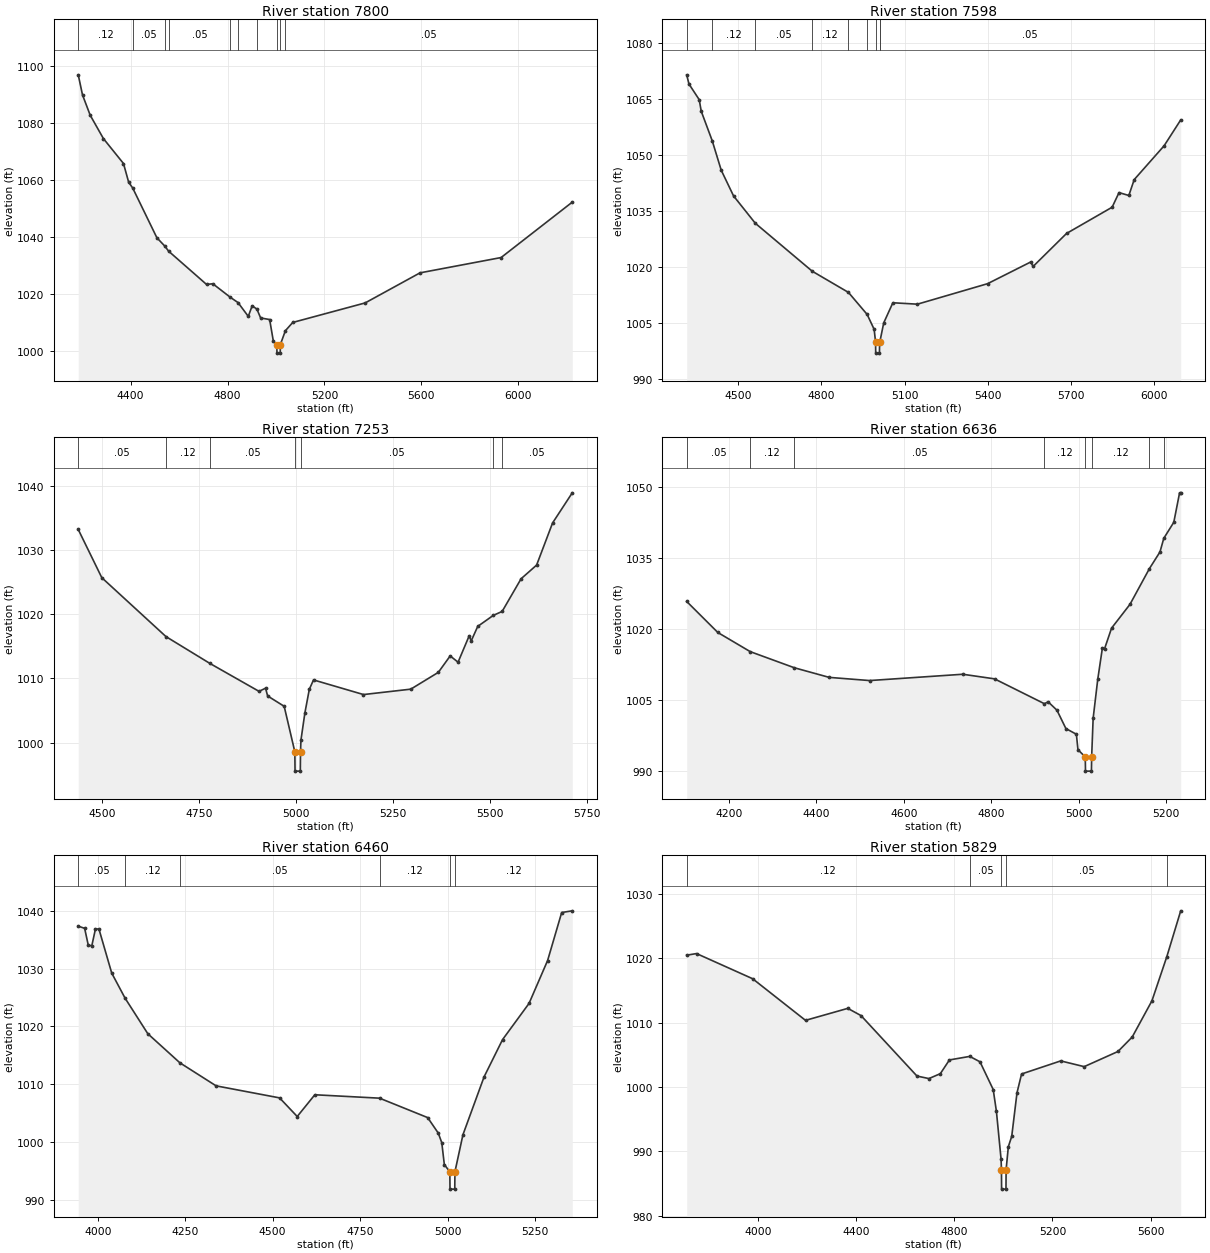
Type RM Length L Ch R = 1,7800,202,202,202
BEGIN DESCRIPTION:
BARNETT BRANCH 16.0
END DESCRIPTION:
XS GIS Cut Line= 3
      2852913.42     10171369.78      2852683.39     10170705.75
      2851997.64     10169559.93
#Sta/Elev= 30
  4184.2 1096.91  4201.8 1089.85  4233.6 1082.70  4288.0 1074.51  4370.9 1065.74
  4392.3 1059.14  4408.9 1057.13  4508.7 1039.64  4541.7 1036.69  4557.0 1034.94
  4713.5 1023.25  4739.4 1023.49  4812.1 1018.70  4843.3 1016.88  4885.7 1012.03
  4901.7 1015.74  4921.2 1014.58  4936.8 1011.46  4973.8 1010.92  4989.3 1003.24
  5003.5 1002.11  5004.0  999.11  5017.5  999.11  5018.0 1002.11  5038.8 1006.99
  5069.1 1009.89  5367.8 1016.75  5594.2 1027.32  5928.7 1032.70  6222.3 1052.17
#Mann=10,-1,0
  4184.2    0.12       0  4408.9    0.05       0  4541.7    0.12       0
  4557.0    0.05       0  4812.1    0.12       0  4843.3    0.05       0
  4921.2    0.12       0  5003.5    0.07       0  5018.0    0.12       0
  5038.8    0.05       0
Bank Sta=5003.5,5018
Exp/Cntr=0.3,0.1

Type RM Length L Ch R = 1,7598,345,345,345
BEGIN DESCRIPTION:
BARNETT BRANCH 15.0
END DESCRIPTION:
XS GIS Cut Line= 3
      2853105.68     10171103.10      2852626.97     10170180.57
      2852362.58     10169487.10
#Sta/Elev= 30
  4314.5 1071.53  4322.7 1069.07  4359.6 1064.89  4367.0 1061.77  4406.5 1053.90
  4439.0 1046.01  4483.5 1039.12  4562.0 1031.80  4767.4 1018.96  4897.8 1013.30
  4965.3 1007.40  4990.5 1003.41  4995.6 1000.05  4996.1  997.05  5009.6  997.05
  5010.1 1000.05  5011.0 1000.06  5025.0 1005.14  5058.0 1010.53  5146.5 1010.15
  5399.4 1015.63  5554.5 1021.42  5563.9 1020.26  5684.3 1029.08  5848.7 1036.10
  5873.5 1040.01  5908.9 1039.24  5928.3 1043.49  6036.1 1052.54  6096.0 1059.46
#Mann=9,-1,0
  4314.5    0.05       0  4406.5    0.12       0  4562.0    0.05       0
  4767.4    0.12       0  4897.8    0.05       0  4965.3    0.12       0
  4995.6    0.07       0  5010.1    0.12       0  5011.0    0.05       0
Bank Sta=4995.6,5010.1
Exp/Cntr=0.3,0.1

Type RM Length L Ch R = 1,7253,617,617,617
BEGIN DESCRIPTION:
BARNETT BRANCH 14.0
END DESCRIPTION:
XS GIS Cut Line= 3
      2853273.69     10170814.29      2853000.23     10170145.85
      2852905.69     10169603.13
#Sta/Elev= 30
  4438.5 1033.20  4499.2 1025.69  4664.6 1016.51  4777.8 1012.33  4904.4 1007.98
  4921.2 1008.47  4926.6 1007.26  4969.2 1005.65  4996.7  998.55  4997.2  995.55
  5010.8  995.55  5011.3  998.55  5012.4 1000.38  5022.6 1004.63  5034.0 1008.30
  5044.8 1009.76  5173.6 1007.48  5295.4 1008.32  5366.5 1010.94  5397.0 1013.50
  5417.3 1012.52  5446.0 1016.64  5451.1 1015.83  5468.0 1018.10  5508.2 1019.82
  5530.9 1020.43  5579.7 1025.52  5619.7 1027.65  5660.9 1034.22  5711.6 1038.91
#Mann=7,-1,0
  4438.5    0.05       0  4664.6    0.12       0  4777.8    0.05       0
  4996.7    0.05       0  5011.3    0.05       0  5508.2    0.12       0
  5530.9    0.05       0
Bank Sta=4996.7,5011.3
Exp/Cntr=0.3,0.1

Type RM Length L Ch R = 1,6636,176,176,176
BEGIN DESCRIPTION:
BARNETT BRANCH 13.0
END DESCRIPTION:
XS GIS Cut Line= 3
      2853455.68     10170753.07      2853279.25     10169874.00
      2853205.69     10169653.13
#Sta/Elev= 30
  4103.4 1025.79  4174.6 1019.24  4248.7 1015.20  4349.8 1011.79  4429.2 1009.77
  4521.5 1009.10  4734.6 1010.43  4807.1 1009.46  4921.3 1004.21  4929.5 1004.63
  4949.9 1002.84  4970.3  998.97  4994.3  997.77  4997.9  994.50  5014.6  992.99
  5015.1  989.99  5028.7  989.99  5029.2  992.99  5032.6 1001.12  5043.1 1009.34
  5053.6 1015.88  5058.8 1015.83  5074.7 1020.16  5116.8 1025.18  5161.2 1032.71
  5185.4 1036.24  5194.1 1039.11  5217.0 1042.50  5230.2 1048.71  5232.8 1048.71
#Mann=8,-1,0
  4103.4    0.05       0  4248.7    0.12       0  4349.8    0.05       0
  4921.3    0.12       0  5014.6    0.07       0  5029.2    0.12       0
  5161.2    0.05       0  5194.1    0.12       0
Bank Sta=5014.6,5029.2
Exp/Cntr=0.3,0.1

Type RM Length L Ch R = 1,6460,631,631,631
BEGIN DESCRIPTION:
BARNETT BRANCH 12.0
END DESCRIPTION:
XS GIS Cut Line= 3
      2853599.20     10170901.07      2853546.34     10170630.08
      2853405.69     10169503.12
#Sta/Elev= 30
  3944.4 1037.35  3962.7 1036.97  3972.9 1034.10  3983.1 1033.94  3993.6 1036.86
  4003.5 1036.86  4040.1 1029.23  4078.1 1024.91  4143.3 1018.74  4235.0 1013.71
  4338.4 1009.73  4519.8 1007.65  4570.2 1004.43  4620.5 1008.19  4805.5 1007.60
  4943.0 1004.24  4973.3 1001.56  4983.3  999.90  4990.6  996.12  5006.3  994.87
  5006.8  991.87  5020.4  991.87  5020.9  994.87  5043.8 1001.28  5104.3 1011.30
  5157.0 1017.73  5232.7 1023.99  5285.7 1031.40  5326.0 1039.71  5356.2 1040.00
#Mann=6,-1,0
  3944.4    0.05       0  4078.1    0.12       0  4235.0    0.05       0
  4805.5    0.12       0  5006.3    0.07       0  5020.9    0.12       0
Bank Sta=5006.3,5020.9
Exp/Cntr=0.3,0.1

Type RM Length L Ch R = 1,5829,497,497,497
BEGIN DESCRIPTION:
BARNETT BRANCH 11.0
END DESCRIPTION:
XS GIS Cut Line= 3
      2854536.71     10171122.46      2853972.46     10169707.48
      2853555.68     10169453.11
#Sta/Elev= 30
  3710.9 1020.45  3751.0 1020.70  3979.3 1016.80  4194.7 1010.34  4366.9 1012.20
  4420.7 1011.08  4648.6 1001.70  4697.2 1001.31  4743.7 1002.07  4780.7 1004.20
  4863.6 1004.75  4905.2 1003.91  4959.0  999.61  4972.1  996.21  4991.0  988.82
  4992.6  987.16  4993.1  984.16  5011.0  984.16  5011.5  987.16  5020.6  990.74
  5034.4  992.35  5055.9  999.11  5074.5 1002.02  5233.9 1004.05  5329.5 1003.16
  5467.0 1005.51  5525.1 1007.76  5605.3 1013.37  5666.1 1020.24  5722.5 1027.33
#Mann=5,-1,0
  3710.9    0.12       0  4863.6    0.05       0  4992.6    0.05       0
  5011.5    0.05       0  5666.1    0.12       0
Bank Sta=4992.6,5011.5
Exp/Cntr=0.3,0.1

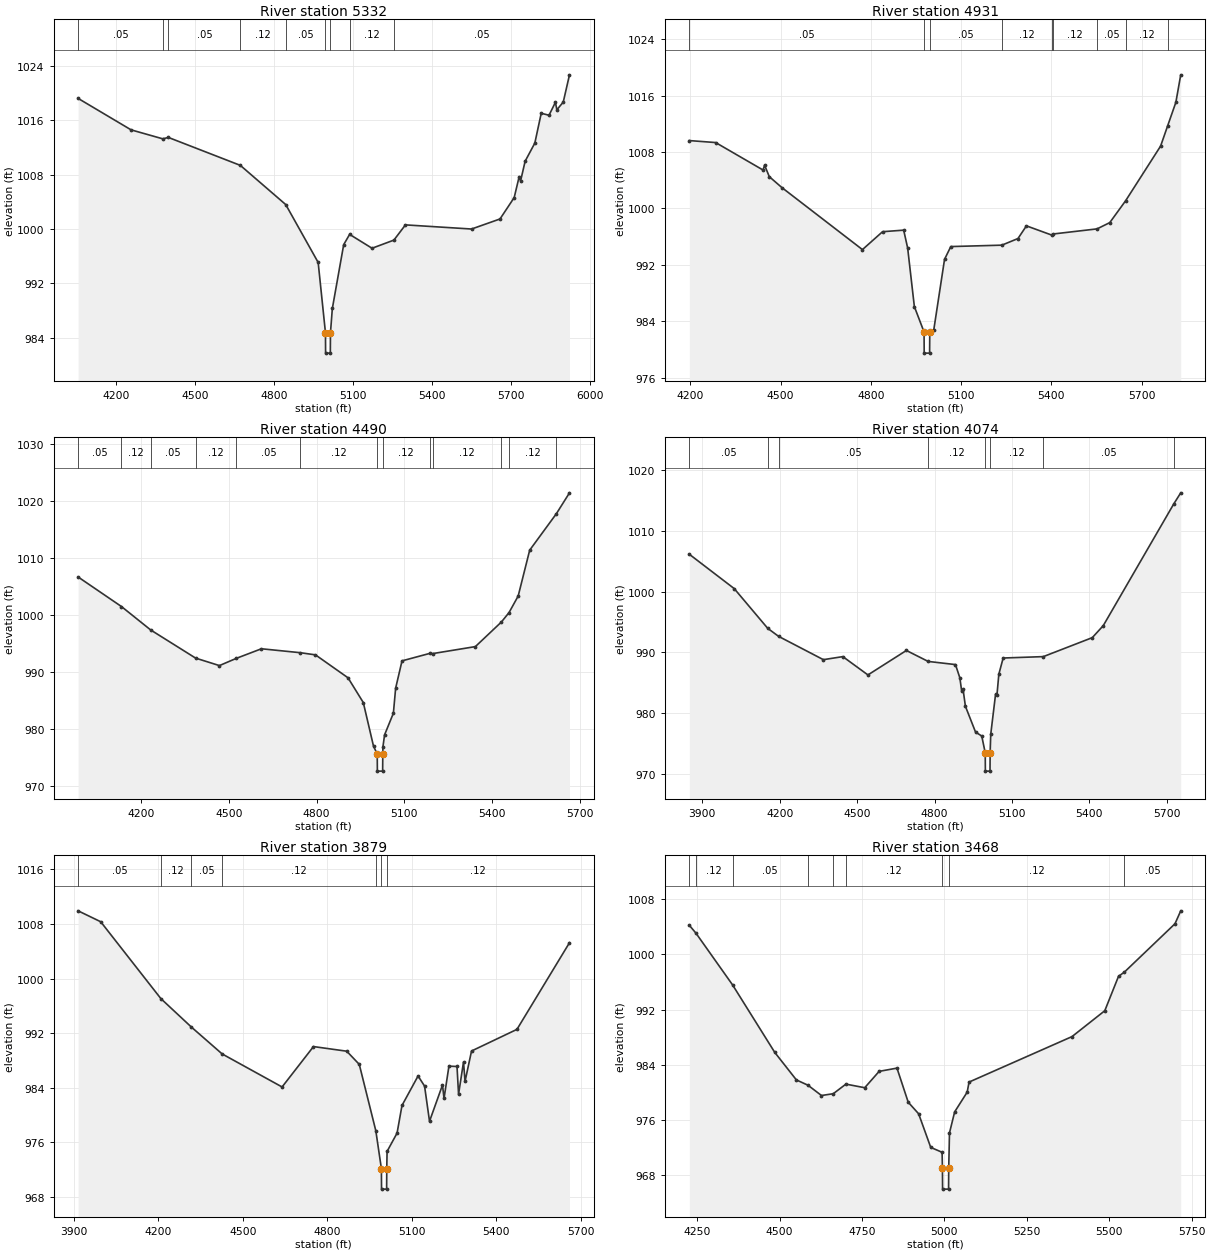
Type RM Length L Ch R = 1,5332,401,401,401
BEGIN DESCRIPTION:
BARNETT BRANCH 10.0
END DESCRIPTION:
XS GIS Cut Line= 3
      2855092.22     10170358.49      2854621.23     10169741.66
      2853609.25     10169339.11
#Sta/Elev= 30
  4057.1 1019.23  4258.1 1014.60  4378.3 1013.28  4399.9 1013.48  4672.9 1009.37
  4845.2 1003.60  4968.3  995.08  4996.0  984.73  4996.5  981.73  5014.5  981.73
  5015.0  984.73  5022.1  988.30  5065.2  997.70  5087.7  999.21  5172.8  997.17
  5255.8  998.37  5299.6 1000.61  5550.5 1000.00  5658.5 1001.48  5712.4 1004.63
  5731.3 1007.71  5736.7 1007.08  5753.9 1009.98  5790.7 1012.65  5815.0 1017.04
  5844.6 1016.75  5868.9 1018.66  5874.3 1017.55  5898.6 1018.69  5922.3 1022.70
#Mann=9,-1,0
  4057.1    0.05       0  4378.3    0.12       0  4399.9    0.05       0
  4672.9    0.12       0  4845.2    0.05       0  4996.0    0.05       0
  5015.0    0.05       0  5087.7    0.12       0  5255.8    0.05       0
Bank Sta=4996,5015
Exp/Cntr=0.3,0.1

Type RM Length L Ch R = 1,4931,441,441,441
BEGIN DESCRIPTION:
Mapping XS bd4db7e4
END DESCRIPTION:
XS GIS Cut Line= 4
      2855226.80     10169334.22      2854580.10     10169212.69
      2854350.06     10169381.96      2853669.66     10169269.28
#Sta/Elev= 30
  4197.0 1009.63  4284.4 1009.35  4442.0 1005.45  4447.0 1006.14  4462.7 1004.51
  4504.6 1002.96  4772.3  994.16  4839.2  996.70  4909.4  996.92  4922.6  994.38
  4944.9  986.07  4977.1  982.47  4977.6  979.47  4995.6  979.47  4996.1  982.47
  5009.5  982.79  5045.2  992.78  5066.0  994.59  5235.6  994.79  5289.3  995.73
  5317.4  997.53  5400.9  996.23  5405.2  996.37  5552.2  997.10  5594.4  997.99
  5646.9 1001.08  5763.4 1008.85  5787.1 1011.76  5814.1 1015.06  5830.3 1018.96
#Mann=9,-1,0
  4197.0    0.05       0  4977.1    0.05       0  4996.1    0.05       0
  5235.6    0.12       0  5400.9    0.05       0  5405.2    0.12       0
  5552.2    0.05       0  5646.9    0.12       0  5787.1    0.05       0
Bank Sta=4977.1,4996.1
Exp/Cntr=0.3,0.1

Type RM Length L Ch R = 1,4490,416,416,416
BEGIN DESCRIPTION:
Mapping XS 3c8daa96
END DESCRIPTION:
XS GIS Cut Line= 4
      2855196.43     10168713.56      2854337.04     10168908.87
      2854085.30     10169047.76      2853594.80     10169186.66
#Sta/Elev= 30
  3985.3 1006.61  4133.3 1001.43  4233.2  997.32  4386.8  992.38  4468.0  991.07
  4526.3  992.35  4611.6  994.02  4744.4  993.33  4796.2  992.95  4907.3  988.93
  4959.5  984.59  4994.4  976.94  5007.1  975.56  5007.6  972.56  5025.6  972.56
  5026.1  975.56  5026.5  976.79  5032.2  978.92  5062.3  982.72  5070.0  987.10
  5091.8  991.90  5186.8  993.21  5197.2  993.18  5342.4  994.40  5431.2  998.71
  5457.4 1000.37  5488.6 1003.27  5527.9 1011.31  5619.1 1017.71  5663.9 1021.37
#Mann=13,-1,0
  3985.3    0.05       0  4133.3    0.12       0  4233.2    0.05       0
  4386.8    0.12       0  4526.3    0.05       0  4744.4    0.12       0
  5007.1    0.07       0  5026.1    0.12       0  5186.8    0.05       0
  5197.2    0.12       0  5431.2    0.05       0  5457.4    0.12       0
  5619.1    0.05       0
Bank Sta=5007.1,5026.1
Exp/Cntr=0.3,0.1

Type RM Length L Ch R = 1,4074,195,195,195
BEGIN DESCRIPTION:
BARNETT BRANCH 9.0
END DESCRIPTION:
XS GIS Cut Line= 3
      2855226.77     10168140.65      2854028.88     10168626.75
      2853581.82     10169043.43
#Sta/Elev= 30
  3849.9 1006.12  4023.7 1000.48  4153.5  993.95  4195.7  992.63  4369.1  988.80
  4444.6  989.30  4541.8  986.29  4690.8  990.31  4775.1  988.51  4881.0  987.99
  4897.9  985.82  4905.1  983.62  4910.5  983.90  4919.5  981.14  4958.7  976.90
  4982.8  976.25  4996.3  973.48  4996.8  970.48  5014.8  970.48  5015.3  973.48
  5017.7  976.56  5036.3  983.10  5041.7  982.97  5049.0  986.41  5065.8  989.07
  5221.4  989.30  5411.1  992.42  5453.6  994.39  5726.4 1014.37  5753.8 1016.22
#Mann=8,-1,0
  3849.9    0.05       0  4153.5    0.12       0  4195.7    0.05       0
  4775.1    0.12       0  4996.3    0.07       0  5015.3    0.12       0
  5221.4    0.05       0  5726.4    0.12       0
Bank Sta=4996.3,5015.3
Exp/Cntr=0.3,0.1

Type RM Length L Ch R = 1,3879,411,411,411
BEGIN DESCRIPTION:
BARNETT BRANCH 8.0
END DESCRIPTION:
XS GIS Cut Line= 3
      2855157.39     10167958.34      2854271.94     10168327.28
      2853555.71     10168653.10
#Sta/Elev= 30
  3914.6 1009.92  3994.9 1008.32  4208.6  997.06  4317.3  992.88  4426.4  988.95
  4639.4  984.11  4751.0  990.03  4869.1  989.35  4913.7  987.42  4972.5  977.69
  4992.3  972.14  4992.8  969.14  5010.9  969.14  5011.4  972.14  5012.5  974.67
  5048.0  977.35  5065.5  981.40  5122.6  985.72  5145.7  984.24  5163.3  979.08
  5209.4  984.39  5214.9  982.44  5232.3  987.16  5261.0  987.11  5266.5  983.04
  5284.1  987.77  5289.5  984.92  5312.6  989.38  5474.0  992.55  5660.7 1005.25
#Mann=7,-1,0
  3914.6    0.05       0  4208.6    0.12       0  4317.3    0.05       0
  4426.4    0.12       0  4972.5    0.05       0  4992.3    0.05       0
  5011.4    0.12       0
Bank Sta=4992.3,5011.4
Exp/Cntr=0.3,0.1

Type RM Length L Ch R = 1,3468,483,483,483
BEGIN DESCRIPTION:
BARNETT BRANCH 7.0
END DESCRIPTION:
XS GIS Cut Line= 3
      2854619.19     10167684.90      2853755.44     10168153.66
      2853357.62     10168469.33
#Sta/Elev= 30
  4226.4 1004.23  4246.6 1003.08  4357.4  995.60  4485.6  985.80  4551.1  981.82
  4586.3  981.05  4627.2  979.56  4662.9  979.82  4701.3  981.21  4758.4  980.69
  4802.1  983.06  4856.2  983.53  4890.3  978.59  4921.9  976.91  4958.6  972.04
  4993.1  971.33  4994.1  968.99  4994.6  965.99  5012.7  965.99  5013.2  968.99
  5015.5  974.14  5031.2  977.19  5069.2  980.05  5074.9  981.51  5387.2  988.10
  5486.6  991.85  5528.2  996.83  5546.3  997.46  5699.6 1004.46  5717.0 1006.33
#Mann=9,-1,0
  4226.4    0.05       0  4246.6    0.12       0  4357.4    0.05       0
  4586.3    0.12       0  4662.9    0.05       0  4701.3    0.12       0
  4994.1    0.07       0  5013.2    0.12       0  5546.3    0.05       0
Bank Sta=4994.1,5013.2
Exp/Cntr=0.3,0.1

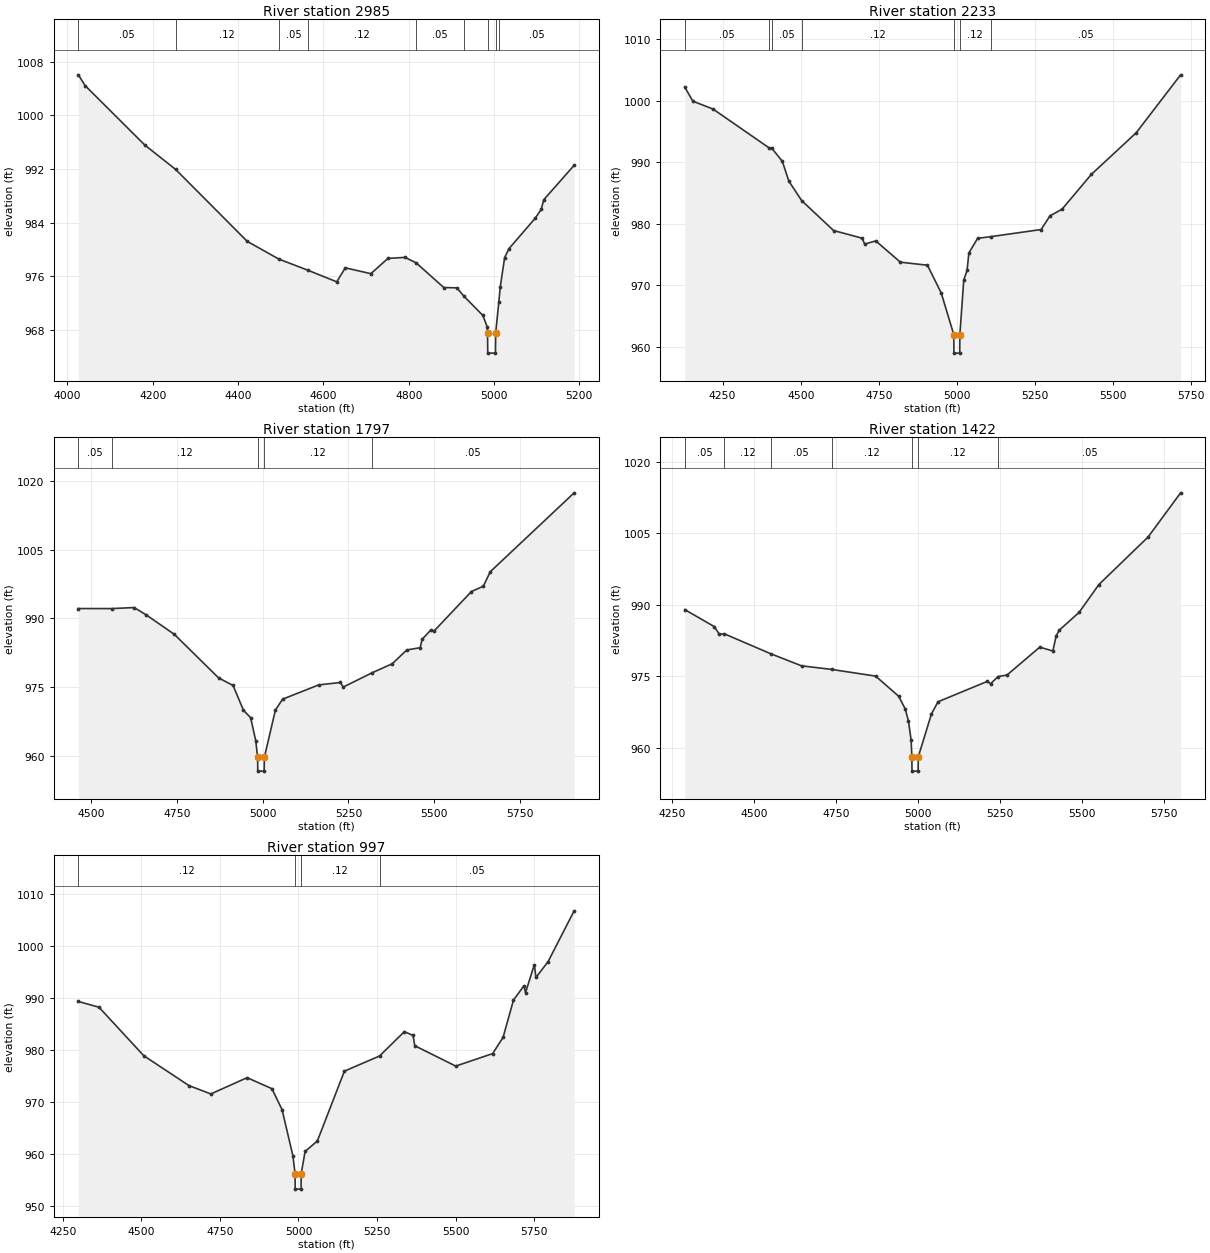
Type RM Length L Ch R = 1,2985,752,752,752
BEGIN DESCRIPTION:
BARNETT BRANCH 6.0
END DESCRIPTION:
XS GIS Cut Line= 3
      2854711.61     10167583.71      2853903.01     10167585.09
      2853555.71     10167653.11
#Sta/Elev= 30
  4025.4 1006.07  4041.3 1004.46  4181.3  995.58  4253.7  991.93  4421.3  981.20
  4495.4  978.55  4563.7  976.88  4631.3  975.15  4651.3  977.24  4711.3  976.37
  4751.3  978.65  4791.3  978.80  4817.3  977.99  4882.2  974.30  4912.8  974.25
  4929.8  972.98  4973.9  970.13  4984.1  968.41  4984.8  967.50  4985.3  964.50
  5003.4  964.50  5003.9  967.50  5011.2  972.09  5014.7  974.42  5024.9  978.77
  5035.1  980.11  5096.2  984.62  5110.7  985.98  5116.6  987.41  5187.9  992.56
#Mann=9,-1,0
  4025.4    0.05       0  4253.7    0.12       0  4495.4    0.05       0
  4563.7    0.12       0  4817.3    0.05       0  4929.8    0.12       0
  4984.8    0.07       0  5003.9    0.12       0  5011.2    0.05       0
Bank Sta=4984.8,5003.9
Exp/Cntr=0.3,0.1

Type RM Length L Ch R = 1,2233,436,436,436
BEGIN DESCRIPTION:
BARNETT BRANCH 5.0
END DESCRIPTION:
XS GIS Cut Line= 3
      2854744.99     10167480.89      2854141.73     10167016.51
      2853409.46     10166635.21
#Sta/Elev= 30
  4129.0 1002.23  4154.8  999.95  4219.2  998.68  4399.4  992.34  4408.1  992.26
  4441.2  990.17  4462.0  986.95  4503.2  983.78  4605.2  978.92  4696.6  977.67
  4704.8  976.72  4740.2  977.23  4819.0  973.77  4905.6  973.28  4949.8  968.75
  4989.9  961.98  4990.4  958.98  5008.9  958.98  5009.4  961.98  5021.8  970.88
  5032.4  972.42  5038.2  975.27  5066.2  977.65  5108.2  977.92  5269.2  979.08
  5297.8  981.30  5336.4  982.39  5430.4  988.06  5573.6  994.81  5715.9 1004.24
#Mann=7,-1,0
  4129.0    0.05       0  4399.4    0.12       0  4408.1    0.05       0
  4503.2    0.12       0  4989.9    0.07       0  5009.4    0.12       0
  5108.2    0.05       0
Bank Sta=4989.9,5009.4
Exp/Cntr=0.3,0.1

Type RM Length L Ch R = 1,1797,375,375,375
BEGIN DESCRIPTION:
BARNETT BRANCH 4.0
END DESCRIPTION:
XS GIS Cut Line= 3
      2854801.48     10166964.45      2854224.19     10166582.48
      2853486.37     10166426.24
#Sta/Elev= 30
  4462.0  992.15  4559.4  992.14  4624.8  992.37  4660.8  990.73  4742.0  986.51
  4871.4  976.97  4913.5  975.32  4943.6  969.91  4964.7  968.27  4979.7  963.17
  4985.0  959.59  4985.5  956.59  5004.1  956.59  5004.6  959.59  5036.9  969.94
  5057.9  972.33  5162.9  975.44  5226.5  975.98  5234.5  974.97  5319.0  978.10
  5377.6  980.07  5420.1  983.09  5459.3  983.59  5464.7  985.40  5490.0  987.44
  5500.2  987.27  5608.7  995.87  5643.3  997.03  5663.8 1000.21  5908.4 1017.46
#Mann=5,-1,0
  4462.0    0.05       0  4559.4    0.12       0  4985.0    0.07       0
  5004.6    0.12       0  5319.0    0.05       0
Bank Sta=4985,5004.6
Exp/Cntr=0.3,0.1

Type RM Length L Ch R = 1,1422,425,425,425
BEGIN DESCRIPTION:
BARNETT BRANCH 3.0
END DESCRIPTION:
XS GIS Cut Line= 3
      2855035.85     10166608.54      2854606.14     10166313.39
      2853616.52     10166283.00
#Sta/Elev= 30
  4289.4  988.99  4379.5  985.41  4394.4  983.83  4410.3  983.89  4551.5  979.71
  4645.4  977.17  4737.0  976.42  4871.2  975.01  4941.2  970.79  4961.2  968.14
  4971.2  965.55  4979.4  961.50  4981.5  958.04  4982.0  955.04  5000.6  955.04
  5001.1  958.04  5041.3  967.07  5061.3  969.62  5211.4  973.90  5221.4  973.41
  5244.6  974.93  5271.4  975.23  5371.4  981.10  5411.4  980.29  5421.5  983.52
  5431.5  984.71  5491.5  988.42  5551.5  994.25  5701.6 1004.25  5800.8 1013.54
#Mann=7,-1,0
  4289.4    0.05       0  4410.3    0.12       0  4551.5    0.05       0
  4737.0    0.12       0  4981.5    0.07       0  5001.1    0.12       0
  5244.6    0.05       0
Bank Sta=4981.5,5001.1
Exp/Cntr=0.3,0.1

Type RM Length L Ch R = 1,997,0,0,0
BEGIN DESCRIPTION:
BARNETT BRANCH 2.0
END DESCRIPTION:
XS GIS Cut Line= 4
      2855135.65     10166330.74      2854623.50     10166100.71
      2854493.29     10165844.64      2853794.50     10166052.97
#Sta/Elev= 30
  4299.4  989.37  4365.1  988.27  4507.6  978.94  4651.6  973.18  4721.1  971.58
  4836.5  974.71  4915.5  972.59  4947.9  968.53  4982.3  959.65  4989.1  956.26
  4989.6  953.26  5008.2  953.26  5008.7  956.26  5021.1  960.51  5060.0  962.52
  5146.2  975.97  5257.9  978.88  5337.0  983.57  5364.8  982.83  5370.1  980.86
  5500.4  976.94  5617.8  979.34  5651.0  982.45  5684.2  989.64  5717.3  992.38
  5722.5  991.07  5750.5  996.46  5755.7  993.99  5794.0  997.01  5877.3 1006.82
#Mann=4,-1,0
  4299.4    0.12       0  4989.1    0.07       0  5008.7    0.12       0
  5257.9    0.05       0
Bank Sta=4989.1,5008.7
Exp/Cntr=0.3,0.1

Chan Stop Cuts=-1