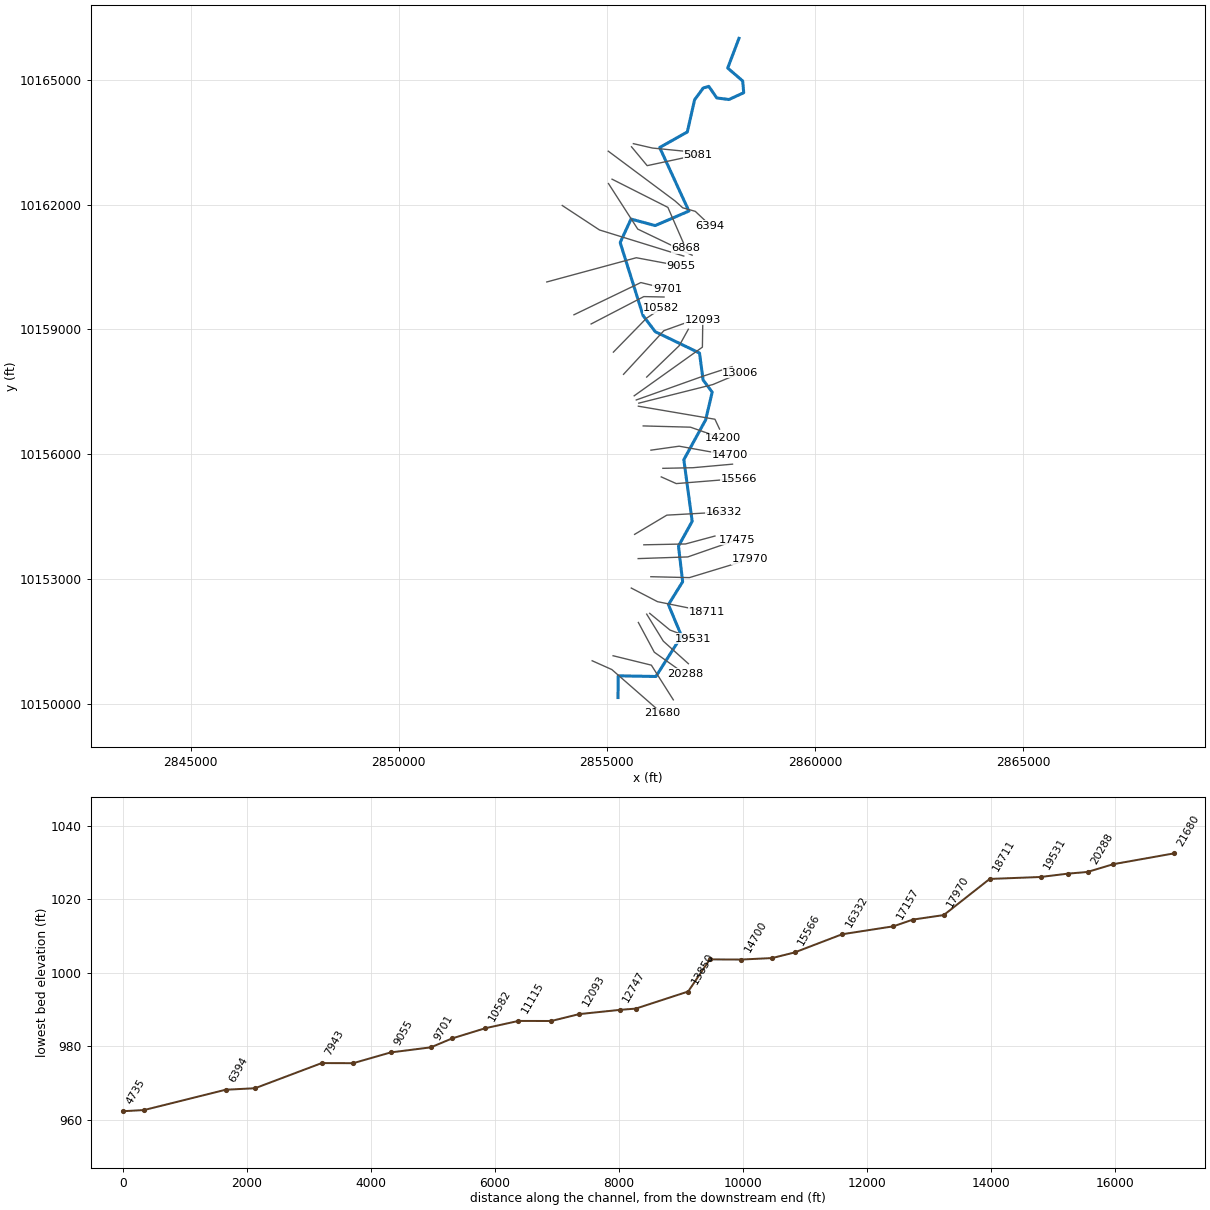
--- COMANCHE CREEK.prj (project) ---

Proj Title=COMANCHE CREEK Base Level Engineering
Current Plan=p01
Default Exp/Contr=0.3,0.1
English Units
Geom File=g01
Flow File=f01
Plan File=p01
BEGIN DESCRIPTION:
COMANCHE CREEK
END DESCRIPTION:

--- COMANCHE CREEK.p01 (plan) ---

Plan Title=Multiple Run
Short Identifier=Multiple
Geom File=g01
Flow File=f01
Subcritical Flow
K Sum by GR= 0
Std Step Tol= 0.01
Critical Tol= 0.01
Num of Std Step Trials= 20
Max Error Tol= 0.3
Flow Tol Ratio= 0.001
Split Flow NTrial= 30
Split Flow Tol= 0.02
Split Flow Ratio= 0.02
Log Output Level= 0
Friction Slope Method= 1
Unsteady Friction Slope Method= 2
Unsteady Bridges Friction Slope Method= 1
Parabolic Critical Depth
Global Vel Dist=  1 , 1 , 1
Global Log Level= 0
CheckData=True
Encroach Param= -1, 0, 0, 0
BEGIN DESCRIPTION:
Multiple Run
END DESCRIPTION:

--- COMANCHE CREEK.f01 (steady flow) ---

Flow Title=Multiple
Number of Profiles=7
Profile Names=10-year,25-year,50-year,1pct_min,100-year,1pct_plu,500-year
River Rch & RM= COMANCHE CREEK,Reach-1,21680
     450    1036    1770     988    2982    9007    8982
River Rch & RM= COMANCHE CREEK,Reach-1,16332
     494    1142    1956    1094    3305    9980    9999
River Rch & RM= COMANCHE CREEK,Reach-1,13850
     533    1238    2125    1191    3597   10862   10922
River Rch & RM= COMANCHE CREEK,Reach-1,8450
     548    1275    2191    1229    3711   11208   11284
River Rch & RM= COMANCHE CREEK,Reach-1,1738
     568    1325    2278    1279    3862   11664   11763
Boundary for River Rch & Prof#=COMANCHE CREEK,Reach-1,1
Up Type=0
Dn Type=3
Dn Slope=0.005
Boundary for River Rch & Prof#=COMANCHE CREEK,Reach-1,2
Up Type=0
Dn Type=3
Dn Slope=0.005
Boundary for River Rch & Prof#=COMANCHE CREEK,Reach-1,3
Up Type=0
Dn Type=3
Dn Slope=0.005
Boundary for River Rch & Prof#=COMANCHE CREEK,Reach-1,4
Up Type=0
Dn Type=3
Dn Slope=0.005
Boundary for River Rch & Prof#=COMANCHE CREEK,Reach-1,5
Up Type=0
Dn Type=3
Dn Slope=0.005
Boundary for River Rch & Prof#=COMANCHE CREEK,Reach-1,6
Up Type=0
Dn Type=3
Dn Slope=0.005
Boundary for River Rch & Prof#=COMANCHE CREEK,Reach-1,7
Up Type=0
Dn Type=3
Dn Slope=0.005

--- COMANCHE CREEK.g01 (geometry) ---

Geom Title=Existing Conditions

River Reach=COMANCHE CREEK,Reach-1
Reach XY= 30
      2855266.50     10150148.00      2855272.50     10150670.00
      2856177.50     10150654.00      2856792.75     10151627.00
      2856477.50     10152382.00      2856819.00     10152932.00
      2856719.50     10153789.00      2857048.00     10154385.00
      2856847.75     10155867.00      2857371.25     10156823.00
      2857529.00     10157490.00      2857311.25     10157781.00
      2857224.25     10158431.00      2856160.50     10158945.00
      2855868.00     10159333.00      2855318.75     10161089.00
      2855579.75     10161652.00      2856160.25     10161496.00
      2856969.25     10161845.00      2856267.75     10163373.00
      2856931.25     10163747.00      2857105.75     10164519.00
      2857313.00     10164803.00      2857446.75     10164844.00
      2857638.50     10164565.00      2857931.75     10164527.00
      2858286.00     10164691.00      2858261.75     10164973.00
      2857901.25     10165283.00      2858172.00     10165998.00

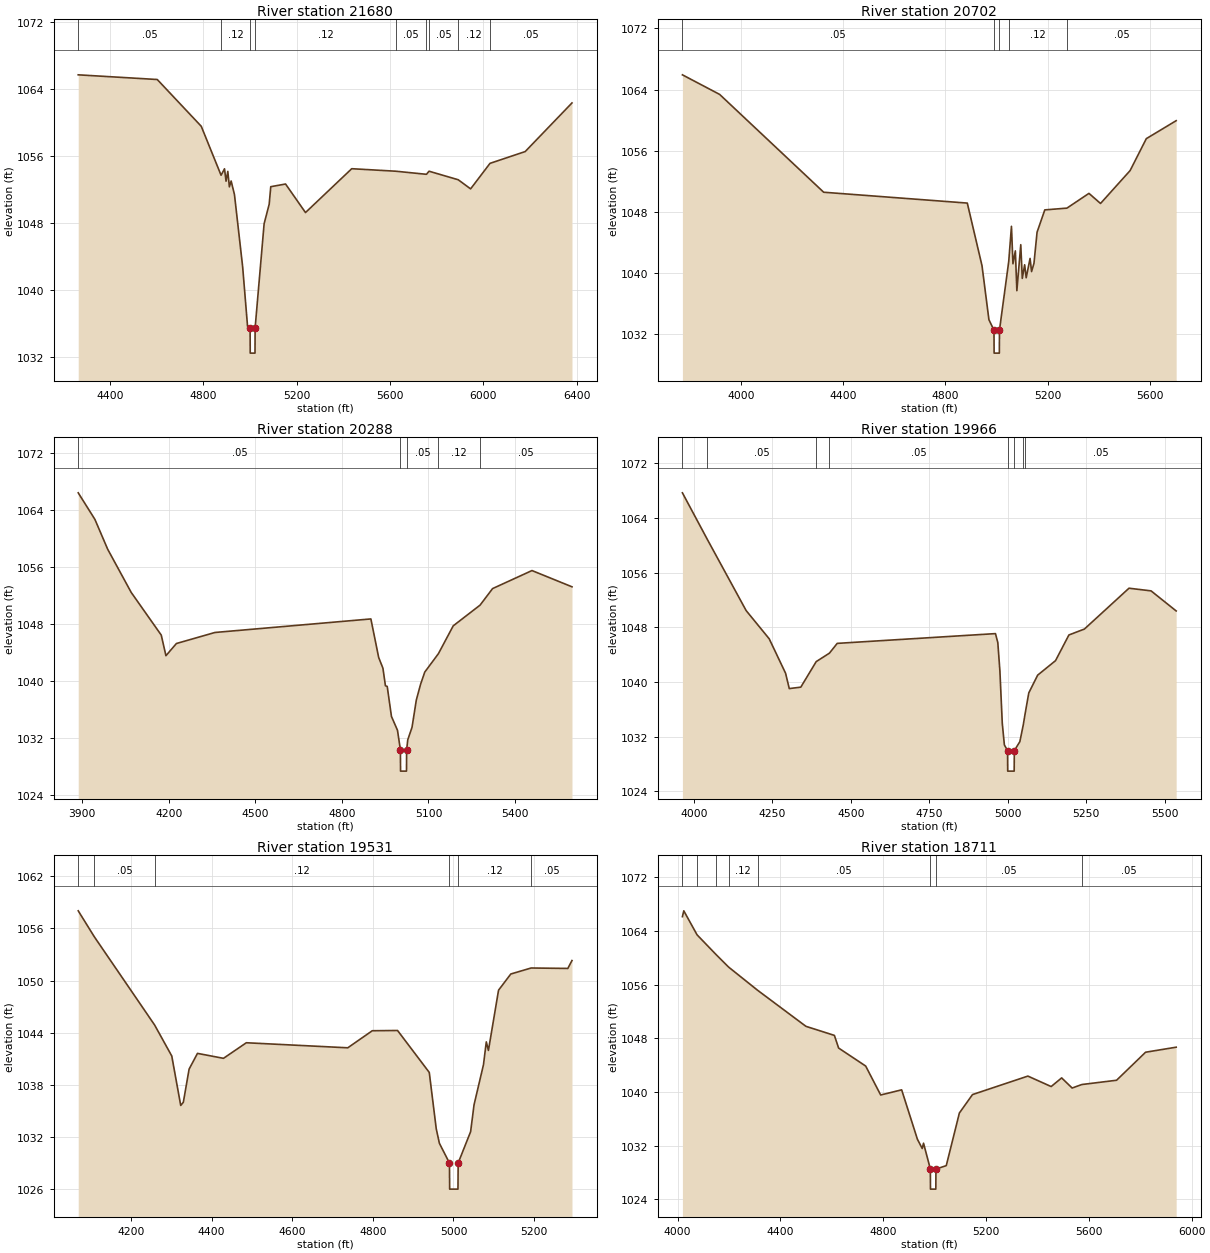
Type RM Length L Ch R = 1,21680,978,978,978
BEGIN DESCRIPTION:
COMANCHE CREEK 37.0
END DESCRIPTION:
XS GIS Cut Line= 3
      2854646.14     10151032.17      2855118.37     10150821.17
      2856322.92     10149767.19
#Sta/Elev= 30
  4262.8 1065.71  4601.8 1065.15  4790.5 1059.56  4875.5 1053.71  4890.2 1054.48
  4896.8 1053.00  4904.4 1054.17  4911.1 1052.32  4918.7 1053.02  4932.9 1051.40
  4968.0 1042.78  4989.1 1035.64  5000.0 1035.45  5000.5 1032.45  5021.0 1032.45
  5021.5 1035.45  5060.1 1047.91  5081.9 1050.25  5088.6 1052.34  5152.1 1052.66
  5237.6 1049.25  5435.9 1054.49  5625.1 1054.19  5756.4 1053.82  5767.5 1054.19
  5892.7 1053.17  5945.8 1052.08  6029.0 1055.13  6180.0 1056.54  6380.6 1062.35
#Mann=9,-1,0
  4262.8    0.05       0  4875.5    0.12       0  5000.0    0.07       0
  5021.5    0.12       0  5625.1    0.05       0  5756.4    0.12       0
  5767.5    0.05       0  5892.7    0.12       0  6029.0    0.05       0
Bank Sta=5000,5021.5
Exp/Cntr=0.3,0.1

Type RM Length L Ch R = 1,20702,414,414,414
BEGIN DESCRIPTION:
COMANCHE CREEK 36.0
END DESCRIPTION:
XS GIS Cut Line= 3
      2855148.55     10151152.72      2856067.84     10150926.67
      2856595.31     10150092.76
#Sta/Elev= 30
  3770.4 1065.92  3916.1 1063.36  4323.5 1050.56  4885.9 1049.14  4943.5 1040.95
  4970.6 1033.88  4990.4 1032.51  4990.9 1029.51  5011.4 1029.51  5011.9 1032.51
  5048.2 1041.51  5058.8 1046.10  5064.7 1041.20  5074.1 1042.89  5080.0 1037.68
  5095.3 1043.70  5101.2 1039.29  5110.5 1041.07  5116.5 1039.37  5131.7 1041.90
  5137.6 1040.18  5147.0 1041.26  5159.1 1045.33  5189.4 1048.25  5276.0 1048.48
  5362.3 1050.41  5407.6 1049.09  5523.4 1053.39  5586.9 1057.57  5703.8 1059.92
#Mann=5,-1,0
  3770.4    0.05       0  4990.4    0.03       0  5011.9    0.05       0
  5048.2    0.12       0  5276.0    0.05       0
Bank Sta=4990.4,5011.9
Exp/Cntr=0.3,0.1

Type RM Length L Ch R = 1,20288,322,322,322
BEGIN DESCRIPTION:
COMANCHE CREEK 35.0
END DESCRIPTION:
XS GIS Cut Line= 3
      2855755.70     10151953.09      2856138.17     10151238.14
      2856871.18     10150715.99
#Sta/Elev= 30
  3886.5 1066.46  3944.2 1062.74  3988.5 1058.55  4070.1 1052.48  4174.2 1046.49
  4190.4 1043.60  4226.7 1045.31  4360.3 1046.86  4900.5 1048.76  4927.6 1043.34
  4942.3 1041.84  4950.9 1039.38  4957.1 1039.29  4971.8 1035.08  4992.7 1033.13
  5002.8 1030.40  5003.3 1027.40  5023.9 1027.40  5024.4 1030.40  5028.4 1031.81
  5043.1 1033.55  5057.9 1037.37  5072.7 1039.59  5087.2 1041.30  5134.6 1043.89
  5185.8 1047.79  5278.9 1050.70  5322.2 1053.02  5458.7 1055.55  5597.3 1053.27
#Mann=5,-1,0
  3886.5    0.05       0  5002.8    0.05       0  5024.4    0.05       0
  5134.6    0.12       0  5278.9    0.05       0
Bank Sta=5002.8,5024.4
Exp/Cntr=0.3,0.1

Type RM Length L Ch R = 1,19966,435,435,435
BEGIN DESCRIPTION:
COMANCHE CREEK 34.0
END DESCRIPTION:
XS GIS Cut Line= 3
      2855955.68     10152153.11      2856354.18     10151504.39
      2856957.04     10150961.82
#Sta/Elev= 30
  3963.6 1067.69  4042.2 1060.93  4166.6 1050.44  4240.0 1046.31  4292.1 1041.27
  4303.9 1039.02  4340.6 1039.23  4389.7 1042.97  4431.8 1044.21  4456.6 1045.64
  4960.5 1047.07  4968.0 1045.76  4974.7 1041.57  4982.2 1033.95  4988.9 1030.77
  4999.0 1029.93  4999.5 1026.93  5020.1 1026.93  5020.6 1029.93  5038.2 1031.25
  5049.2 1033.73  5054.6 1035.24  5066.6 1038.38  5095.0 1040.99  5151.8 1043.11
  5194.4 1046.87  5243.8 1047.74  5385.8 1053.72  5456.0 1053.33  5536.0 1050.39
#Mann=8,-1,0
  3963.6    0.12       0  4042.2    0.05       0  4389.7    0.12       0
  4431.8    0.05       0  4999.0    0.03       0  5020.6    0.05       0
  5049.2    0.12       0  5054.6    0.05       0
Bank Sta=4999,5020.6
Exp/Cntr=0.3,0.1

Type RM Length L Ch R = 1,19531,820,820,820
BEGIN DESCRIPTION:
COMANCHE CREEK 33.0
END DESCRIPTION:
XS GIS Cut Line= 3
      2856027.66     10152172.52      2856514.94     10151770.64
      2857071.65     10151565.01
#Sta/Elev= 30
  4069.0 1058.01  4108.9 1055.03  4258.4 1044.90  4301.1 1041.33  4323.3 1035.65
  4329.8 1036.01  4344.1 1039.82  4364.9 1041.63  4429.4 1041.06  4486.1 1042.85
  4737.8 1042.27  4798.6 1044.23  4861.3 1044.26  4940.0 1039.44  4957.3 1032.97
  4965.1 1031.30  4990.1 1029.03  4990.6 1026.03  5011.2 1026.03  5011.7 1029.03
  5042.6 1032.63  5051.1 1035.72  5074.5 1040.33  5081.5 1042.95  5086.8 1041.97
  5111.9 1048.89  5142.3 1050.75  5192.8 1051.44  5283.8 1051.39  5294.1 1052.30
#Mann=6,-1,0
  4069.0    0.12       0  4108.9    0.05       0  4258.4    0.12       0
  4990.1    0.07       0  5011.7    0.12       0  5192.8    0.05       0
Bank Sta=4990.1,5011.7
Exp/Cntr=0.3,0.1

Type RM Length L Ch R = 1,18711,741,741,741
BEGIN DESCRIPTION:
COMANCHE CREEK 32.0
END DESCRIPTION:
XS GIS Cut Line= 3
      2855585.56     10152780.39      2856216.06     10152452.85
      2857402.37     10152213.08
#Sta/Elev= 30
  4019.0 1066.14  4024.4 1067.01  4076.0 1063.43  4150.1 1060.48  4198.4 1058.63
  4312.2 1055.14  4499.6 1049.78  4610.2 1048.43  4626.7 1046.54  4731.9 1043.86
  4790.3 1039.54  4871.9 1040.31  4933.2 1032.94  4951.9 1031.56  4957.0 1032.35
  4983.5 1028.50  4984.0 1025.50  5004.8 1025.50  5005.3 1028.50  5045.4 1029.00
  5096.4 1036.85  5147.4 1039.60  5362.9 1042.36  5453.5 1040.80  5494.3 1042.09
  5535.1 1040.58  5572.7 1041.10  5708.0 1041.74  5820.8 1045.92  5939.8 1046.67
#Mann=8,-1,0
  4019.0    0.05       0  4076.0    0.12       0  4150.1    0.05       0
  4198.4    0.12       0  4312.2    0.05       0  4983.5    0.07       0
  5005.3    0.05       0  5572.7    0.05       0
Bank Sta=4983.5,5005.3
Exp/Cntr=0.3,0.1

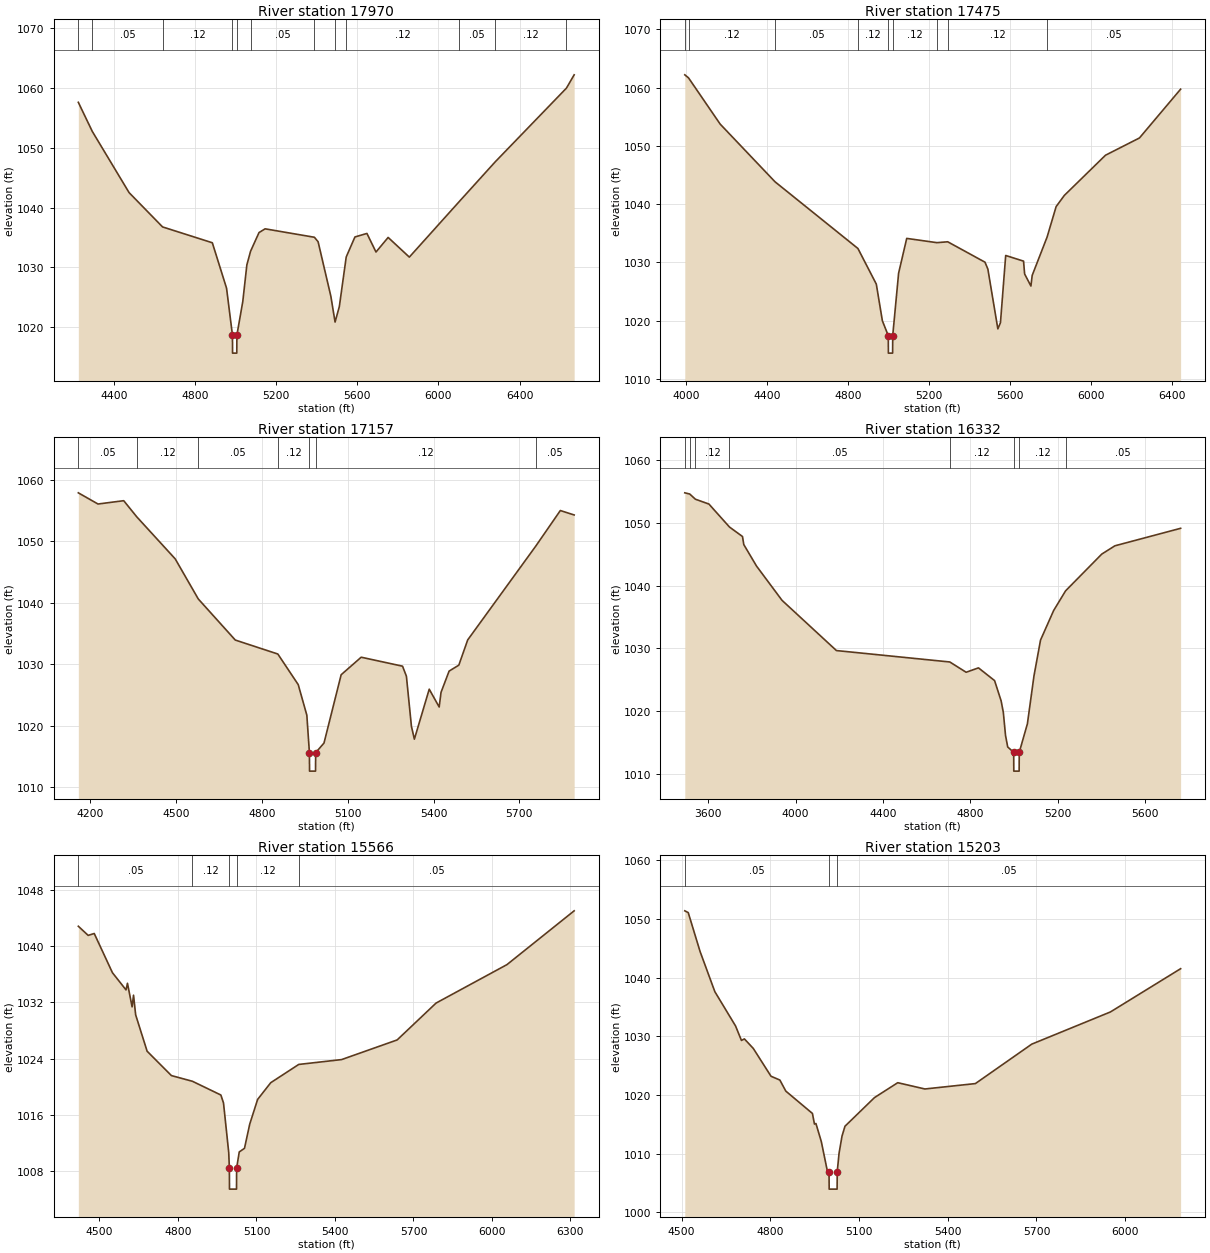
Type RM Length L Ch R = 1,17970,495,495,495
BEGIN DESCRIPTION:
COMANCHE CREEK 31.0
END DESCRIPTION:
XS GIS Cut Line= 3
      2856055.73     10153053.11      2856982.14     10153031.58
      2858432.34     10153473.16
#Sta/Elev= 30
  4225.7 1057.61  4294.4 1052.75  4475.7 1042.51  4640.6 1036.77  4885.8 1034.12
  4955.9 1026.52  4985.0 1018.66  4985.5 1015.66  5006.3 1015.66  5006.8 1018.66
  5035.9 1024.30  5055.9 1030.41  5074.2 1032.70  5115.9 1035.83  5145.9 1036.45
  5388.7 1035.04  5406.9 1034.29  5469.7 1025.18  5490.5 1020.86  5511.5 1023.45
  5545.4 1031.74  5588.3 1035.09  5647.4 1035.68  5692.1 1032.57  5751.9 1035.01
  5856.3 1031.72  6101.7 1040.99  6279.0 1047.64  6630.4 1059.99  6668.3 1062.21
#Mann=12,-1,0
  4225.7    0.12       0  4294.4    0.05       0  4640.6    0.12       0
  4985.0    0.07       0  5006.8    0.12       0  5074.2    0.05       0
  5388.7    0.12       0  5490.5    0.05       0  5545.4    0.12       0
  6101.7    0.05       0  6279.0    0.12       0  6630.4    0.05       0
Bank Sta=4985,5006.8
Exp/Cntr=0.3,0.1

Type RM Length L Ch R = 1,17475,318,318,318
BEGIN DESCRIPTION:
COMANCHE CREEK 30.0
END DESCRIPTION:
XS GIS Cut Line= 3
      2855751.31     10153488.73      2856941.95     10153528.92
      2858127.51     10153940.85
#Sta/Elev= 30
  3994.4 1062.18  4012.8 1061.66  4168.9 1053.73  4439.3 1043.84  4848.6 1032.39
  4939.3 1026.28  4969.3 1019.98  4998.4 1017.44  4998.9 1014.44  5019.8 1014.44
  5020.3 1017.44  5049.4 1028.16  5089.4 1034.12  5238.3 1033.39  5291.6 1033.54
  5475.5 1030.04  5489.7 1028.87  5539.0 1018.60  5551.9 1019.66  5577.7 1031.19
  5665.8 1030.22  5671.1 1028.02  5702.2 1025.95  5708.4 1027.77  5782.0 1034.35
  5826.6 1039.58  5867.2 1041.50  6070.2 1048.39  6237.7 1051.35  6440.8 1059.72
#Mann=9,-1,0
  3994.4    0.05       0  4012.8    0.12       0  4439.3    0.05       0
  4848.6    0.12       0  4998.4    0.07       0  5020.3    0.12       0
  5238.3    0.05       0  5291.6    0.12       0  5782.0    0.05       0
Bank Sta=4998.4,5020.3
Exp/Cntr=0.3,0.1

Type RM Length L Ch R = 1,17157,825,825,825
BEGIN DESCRIPTION:
COMANCHE CREEK 29.0
END DESCRIPTION:
XS GIS Cut Line= 3
      2855886.99     10153820.29      2856886.69     10153840.38
      2857595.02     10154031.28
#Sta/Elev= 30
  4158.2 1057.87  4226.9 1056.05  4316.9 1056.59  4362.4 1053.97  4497.0 1047.12
  4577.5 1040.61  4707.0 1033.92  4855.7 1031.65  4927.0 1026.67  4957.1 1021.70
  4966.1 1015.60  4966.6 1012.60  4987.5 1012.60  4988.0 1015.60  5017.1 1017.17
  5077.1 1028.28  5147.1 1031.13  5291.7 1029.67  5305.2 1028.04  5322.8 1019.88
  5333.1 1017.80  5385.0 1025.93  5419.8 1023.03  5426.3 1025.42  5454.5 1028.87
  5488.5 1029.84  5519.5 1033.94  5757.9 1049.23  5843.4 1054.99  5891.7 1054.27
#Mann=7,-1,0
  4158.2    0.05       0  4362.4    0.12       0  4577.5    0.05       0
  4855.7    0.12       0  4966.1    0.07       0  4988.0    0.12       0
  5757.9    0.05       0
Bank Sta=4966.1,4988
Exp/Cntr=0.3,0.1

Type RM Length L Ch R = 1,16332,766,766,766
BEGIN DESCRIPTION:
COMANCHE CREEK 28.0
END DESCRIPTION:
XS GIS Cut Line= 3
      2855665.93     10154071.46      2856439.59     10154533.64
      2857806.01     10154609.00
#Sta/Elev= 30
  3493.2 1054.83  3515.7 1054.64  3541.8 1053.81  3603.6 1053.04  3697.6 1049.38
  3757.3 1047.86  3763.2 1046.58  3821.5 1043.15  3938.3 1037.68  4187.3 1029.67
  4706.3 1027.85  4781.1 1026.21  4837.5 1026.91  4911.3 1024.88  4941.3 1021.64
  4951.3 1019.81  4961.4 1016.13  4971.4 1014.29  4998.7 1013.44  4999.2 1010.44
  5023.7 1010.44  5024.2 1013.44  5061.5 1017.99  5091.6 1025.63  5121.6 1031.34
  5181.7 1036.06  5236.4 1039.20  5402.0 1045.06  5462.1 1046.38  5762.9 1049.17
#Mann=8,-1,0
  3493.2    0.12       0  3515.7    0.05       0  3541.8    0.12       0
  3697.6    0.05       0  4706.3    0.12       0  4998.7    0.07       0
  5024.2    0.12       0  5236.4    0.05       0
Bank Sta=4998.7,5024.2
Exp/Cntr=0.3,0.1

Type RM Length L Ch R = 1,15566,363,363,363
BEGIN DESCRIPTION:
COMANCHE CREEK 27.0
END DESCRIPTION:
XS GIS Cut Line= 3
      2856305.65     10155453.13      2856665.65     10155292.21
      2858161.68     10155412.70
#Sta/Elev= 30
  4419.1 1042.83  4456.7 1041.53  4479.9 1041.80  4549.5 1036.23  4601.4 1033.79
  4606.9 1034.73  4624.6 1031.38  4630.1 1033.04  4638.2 1030.25  4682.0 1025.08
  4774.8 1021.62  4855.1 1020.81  4963.9 1018.86  4974.0 1017.73  4994.0 1010.67
  4996.4 1008.49  4996.9 1005.49  5023.7 1005.49  5024.2 1008.49  5034.2 1010.77
  5054.2 1011.29  5074.3 1014.73  5104.4 1018.23  5154.6 1020.61  5261.6 1023.20
  5425.4 1023.89  5637.7 1026.68  5786.6 1031.92  6057.5 1037.38  6314.3 1045.02
#Mann=5,-1,0
  4419.1    0.05       0  4855.1    0.12       0  4996.4    0.07       0
  5024.2    0.12       0  5261.6    0.05       0
Bank Sta=4996.4,5024.2
Exp/Cntr=0.3,0.1

Type RM Length L Ch R = 1,15203,503,503,503
BEGIN DESCRIPTION:
COMANCHE CREEK 26.0
END DESCRIPTION:
XS GIS Cut Line= 3
      2856344.11     10155658.94      2857067.54     10155674.01
      2858017.02     10155759.41
#Sta/Elev= 30
  4510.7 1051.37  4522.3 1051.07  4562.3 1044.45  4612.3 1037.60  4682.3 1031.76
  4702.3 1029.29  4712.3 1029.55  4742.3 1027.93  4802.3 1023.19  4832.3 1022.54
  4852.3 1020.66  4942.4 1016.85  4949.2 1015.04  4954.2 1015.14  4972.4 1012.06
  4992.4 1007.15  4998.5 1006.96  4999.0 1003.96  5025.8 1003.96  5026.3 1006.96
  5032.4 1010.06  5042.4 1012.99  5052.4 1014.67  5152.4 1019.56  5230.9 1022.09
  5322.8 1021.02  5493.5 1021.94  5684.2 1028.66  5950.1 1034.14  6187.6 1041.51
#Mann=3,-1,0
  4510.7    0.05       0  4998.5    0.03       0  5026.3    0.05       0
Bank Sta=4998.5,5026.3
Exp/Cntr=0.3,0.1

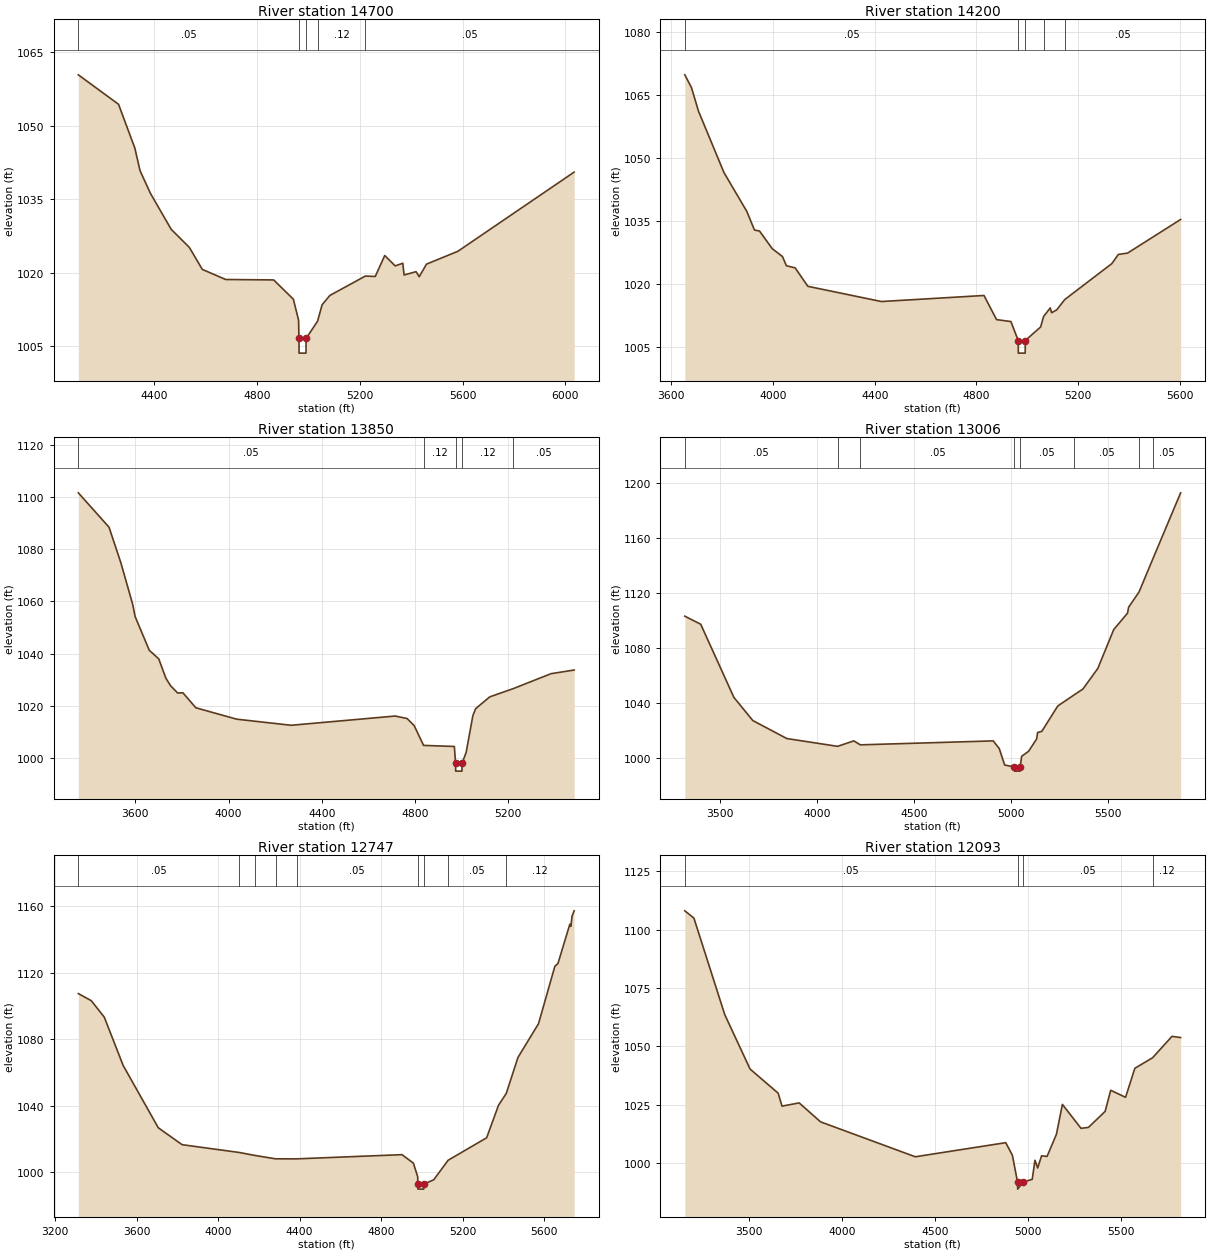
Type RM Length L Ch R = 1,14700,500,500,500
BEGIN DESCRIPTION:
COMANCHE CREEK 25.0
END DESCRIPTION:
XS GIS Cut Line= 3
      2856057.79     10156096.00      2856735.98     10156191.45
      2857961.24     10155970.50
#Sta/Elev= 30
  4103.9 1060.43  4260.4 1054.41  4323.9 1045.45  4344.1 1040.84  4384.5 1036.21
  4465.3 1028.86  4536.0 1025.16  4586.5 1020.66  4677.4 1018.60  4864.3 1018.51
  4940.9 1014.57  4961.2 1010.28  4962.6 1006.55  4963.1 1003.55  4990.0 1003.55
  4990.5 1006.55  5035.1 1010.08  5052.7 1013.43  5083.2 1015.35  5221.1 1019.30
  5259.7 1019.22  5296.5 1023.50  5337.2 1021.38  5366.8 1021.92  5371.9 1019.52
  5418.5 1020.20  5430.6 1019.16  5459.1 1021.74  5581.1 1024.36  6033.8 1040.55
#Mann=5,-1,0
  4103.9    0.05       0  4962.6    0.05       0  4990.5    0.05       0
  5035.1    0.12       0  5221.1    0.05       0
Bank Sta=4962.6,4990.5
Exp/Cntr=0.3,0.1

Type RM Length L Ch R = 1,14200,350,350,350
BEGIN DESCRIPTION:
COMANCHE CREEK 24.0
END DESCRIPTION:
XS GIS Cut Line= 3
      2855871.91     10156678.74      2857007.26     10156648.60
      2857774.72     10156377.73
#Sta/Elev= 30
  3653.3 1069.79  3679.5 1066.76  3707.1 1061.16  3807.1 1046.57  3897.2 1037.30
  3927.2 1032.89  3947.2 1032.63  3997.2 1028.44  4037.2 1026.58  4053.0 1024.38
  4087.2 1023.88  4137.2 1019.49  4426.4 1015.87  4829.8 1017.31  4879.1 1011.57
  4935.6 1011.11  4964.3 1006.60  4964.8 1003.60  4991.7 1003.60  4992.2 1006.60
  5052.5 1009.83  5064.1 1012.31  5090.3 1014.36  5095.6 1013.20  5115.9 1013.90
  5147.1 1016.33  5332.4 1024.89  5358.0 1027.07  5394.3 1027.39  5602.9 1035.39
#Mann=5,-1,0
  3653.3    0.05       0  4964.3    0.03       0  4992.2    0.05       0
  5064.1    0.12       0  5147.1    0.05       0
Bank Sta=4964.3,4992.2
Exp/Cntr=0.3,0.1

Type RM Length L Ch R = 1,13850,844,844,844
BEGIN DESCRIPTION:
COMANCHE CREEK 23.0
END DESCRIPTION:
XS GIS Cut Line= 3
      2855755.66     10157153.12      2857595.02     10156839.49
      2857705.68     10156603.13
#Sta/Elev= 30
  3355.4 1101.68  3487.3 1088.45  3538.0 1074.78  3588.7 1058.84  3598.9 1054.21
  3659.8 1041.24  3700.3 1037.95  3730.8 1030.55  3751.1 1027.63  3781.5 1024.84
  3804.2 1024.91  3859.4 1019.17  4034.8 1014.79  4268.4 1012.45  4714.8 1016.00
  4765.5 1015.05  4795.9 1012.35  4836.4 1004.73  4968.4 1004.31  4973.6  997.85
  4974.1  994.85  5001.0  994.85  5001.5  997.85  5019.1 1002.07  5047.8 1016.15
  5059.7 1018.83  5120.5 1023.37  5220.5 1026.50  5382.9 1032.25  5482.3 1033.66
#Mann=5,-1,0
  3355.4    0.05       0  4836.4    0.12       0  4973.6    0.07       0
  5001.5    0.12       0  5220.5    0.05       0
Bank Sta=4973.6,5001.5
Exp/Cntr=0.3,0.1

Type RM Length L Ch R = 1,13006,259,259,259
BEGIN DESCRIPTION:
COMANCHE CREEK 22.0
END DESCRIPTION:
XS GIS Cut Line= 3
      2855766.40     10157226.31      2857544.79     10157673.42
      2858205.70     10157953.12
#Sta/Elev= 30
  3320.3 1103.17  3402.1 1097.32  3573.0 1043.95  3670.1 1027.10  3845.4 1013.95
  4106.6 1008.27  4189.9 1012.26  4223.6 1009.36  4907.5 1012.24  4938.4 1006.66
  4966.2  994.67  5016.7  993.20  5017.2  990.20  5045.3  990.20  5045.8  993.20
  5053.6 1000.99  5089.6 1004.70  5130.7 1013.64  5135.9 1018.38  5157.2 1019.18
  5239.7 1037.73  5322.3 1045.65  5369.0 1050.08  5445.5 1065.03  5527.5 1093.42
  5598.5 1105.38  5604.0 1109.68  5657.6 1120.78  5729.7 1145.24  5871.7 1193.11
#Mann=8,-1,0
  3320.3    0.05       0  4106.6    0.12       0  4223.6    0.05       0
  5016.7    0.05       0  5045.8    0.05       0  5322.3    0.05       0
  5657.6    0.12       0  5729.7    0.05       0
Bank Sta=5016.7,5045.8
Exp/Cntr=0.3,0.1

Type RM Length L Ch R = 1,12747,654,654,654
BEGIN DESCRIPTION:
COMANCHE CREEK 21.0
END DESCRIPTION:
XS GIS Cut Line= 3
      2855705.70     10157303.12      2857294.50     10157870.00
      2858005.67     10158103.11
#Sta/Elev= 30
  3313.1 1107.58  3376.8 1103.28  3440.5 1093.40  3533.5 1064.25  3705.9 1026.78
  3822.7 1016.61  4103.1 1011.92  4179.1 1010.16  4282.3 1008.08  4385.6 1008.07
  4902.7 1010.60  4958.8 1005.51  4980.0  997.31  4980.6  992.85  4981.1  989.85
  5009.2  989.85  5009.7  992.85  5058.6  995.45  5129.2 1007.22  5318.6 1020.76
  5377.0 1040.38  5414.7 1047.41  5472.5 1069.16  5573.3 1089.43  5653.7 1124.01
  5668.8 1125.69  5727.2 1149.32  5732.5 1148.05  5737.9 1154.15  5748.4 1157.39
#Mann=9,-1,0
  3313.1    0.05       0  4103.1    0.12       0  4179.1    0.05       0
  4282.3    0.12       0  4385.6    0.05       0  4980.6    0.03       0
  5009.7    0.05       0  5129.2    0.05       0  5414.7    0.12       0
Bank Sta=4980.6,5009.7
Exp/Cntr=0.3,0.1

Type RM Length L Ch R = 1,12093,449,449,449
BEGIN DESCRIPTION:
COMANCHE CREEK 20.0
END DESCRIPTION:
XS GIS Cut Line= 3
      2855655.70     10157403.12      2857293.60     10158572.65
      2857303.63     10159229.48
#Sta/Elev= 30
  3153.4 1108.08  3202.5 1104.97  3368.5 1063.56  3504.9 1040.21  3656.0 1029.86
  3676.9 1024.30  3769.1 1025.69  3884.6 1017.55  4394.4 1002.58  4881.3 1008.63
  4917.0 1003.27  4945.0  991.70  4945.5  988.70  4974.3  991.70  5023.9  992.91
  5038.6 1001.08  5053.4  997.77  5074.3 1003.00  5103.8 1002.73  5154.2 1012.22
  5186.5 1025.05  5286.5 1014.79  5326.5 1015.18  5416.5 1022.04  5446.5 1031.10
  5526.5 1028.09  5576.5 1040.54  5672.1 1045.06  5776.5 1054.24  5822.9 1053.72
#Mann=4,-1,0
  3153.4    0.05       0  4945.0    0.05       0  4974.3    0.05       0
  5672.1    0.12       0
Bank Sta=4945,4974.3
Exp/Cntr=0.3,0.1

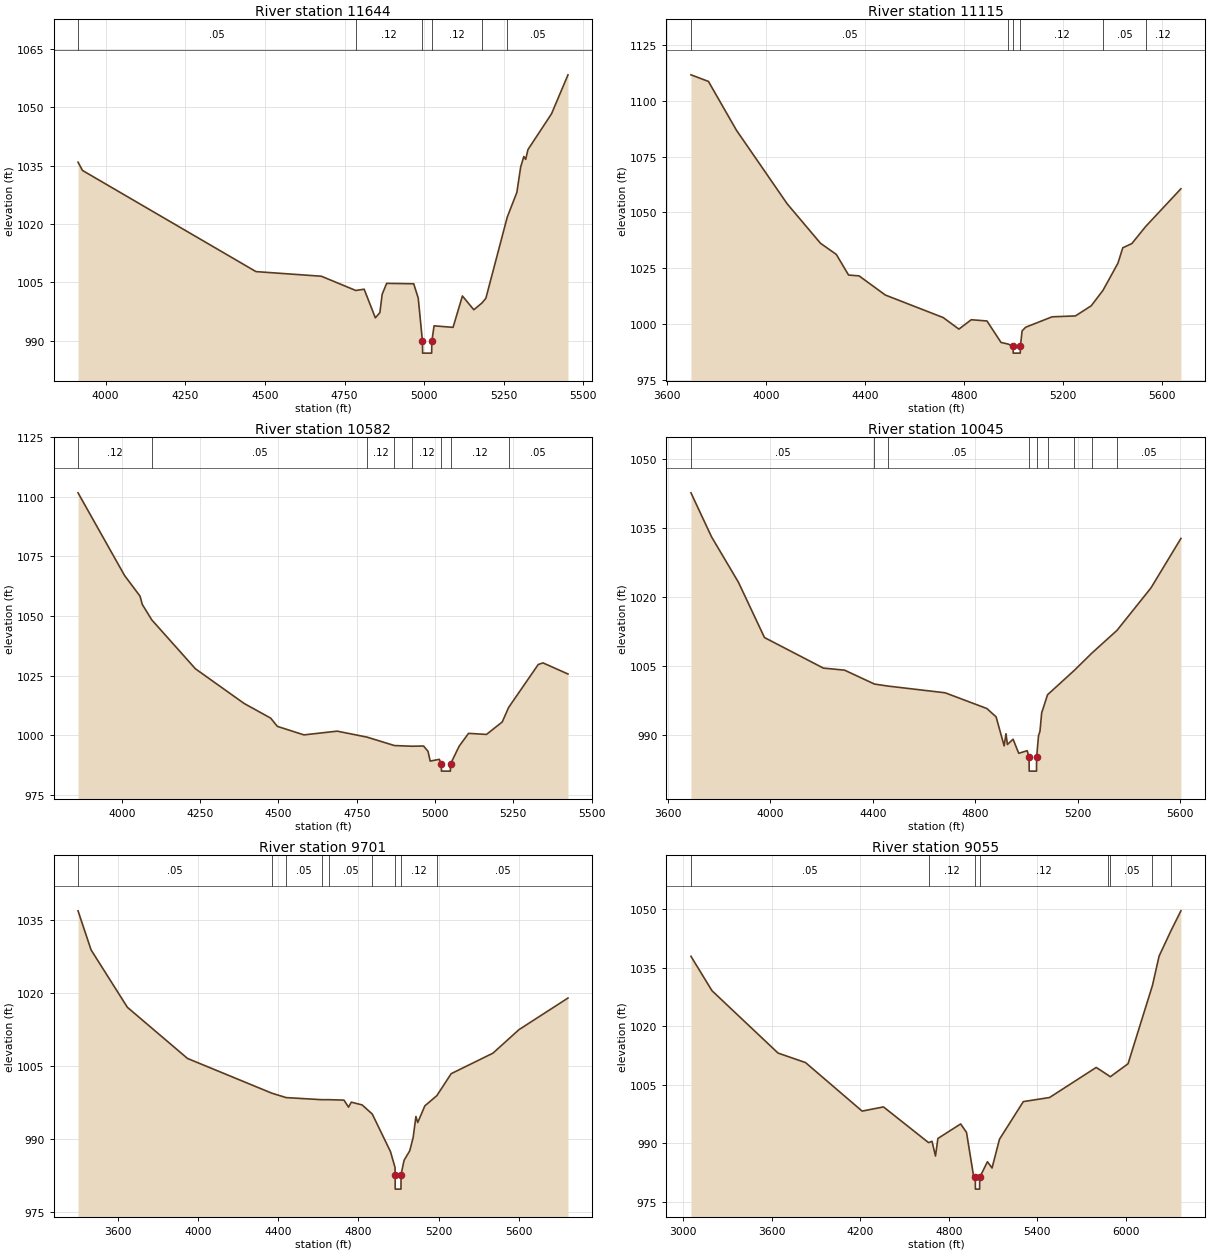
Type RM Length L Ch R = 1,11644,529,529,529
BEGIN DESCRIPTION:
COMANCHE CREEK 19.0
END DESCRIPTION:
XS GIS Cut Line= 3
      2855955.68     10157853.11      2856737.25     10158608.00
      2856955.70     10159003.14
#Sta/Elev= 30
  3913.4 1035.88  3927.4 1033.75  4472.0 1007.77  4677.3 1006.58  4785.4 1002.92
  4811.6 1003.25  4846.8  995.89  4861.0  997.24  4868.2 1001.96  4882.3 1004.75
  4967.2 1004.64  4981.4 1000.96  4994.7  989.83  4995.2  986.83  5023.5  986.83
  5024.0  989.83  5031.1  993.84  5090.7  993.45  5120.1 1001.51  5155.9  997.97
  5181.3  999.70  5193.7 1000.91  5260.9 1021.78  5291.1 1028.14  5302.9 1034.61
  5312.9 1037.34  5318.6 1036.60  5325.8 1039.10  5399.9 1048.31  5451.5 1058.31
#Mann=6,-1,0
  3913.4    0.05       0  4785.4    0.12       0  4994.7    0.07       0
  5024.0    0.12       0  5181.3    0.12       0  5260.9    0.05       0
Bank Sta=4994.7,5024
Exp/Cntr=0.3,0.1

Type RM Length L Ch R = 1,11115,533,533,533
BEGIN DESCRIPTION:
COMANCHE CREEK 18.0
END DESCRIPTION:
XS GIS Cut Line= 3
      2855399.69     10157919.58      2856369.25     10158969.52
      2856886.65     10159155.38
#Sta/Elev= 30
  3697.1 1111.78  3767.7 1108.82  3880.6 1086.94  4085.8 1053.86  4220.2 1036.17
  4284.3 1031.14  4333.6 1021.90  4376.1 1021.52  4482.2 1012.92  4715.8 1002.81
  4779.3  997.62  4829.2 1001.83  4892.7 1001.27  4949.4  991.64  4979.1  990.88
  4998.2  989.84  4998.7  986.84  5027.1  986.84  5027.6  989.84  5034.5  996.81
  5048.6  998.45  5155.6 1003.14  5249.9 1003.54  5313.7 1008.08  5361.6 1015.09
  5421.6 1027.21  5441.2 1034.14  5477.7 1036.01  5533.4 1043.66  5676.0 1060.64
#Mann=6,-1,0
  3697.1    0.05       0  4979.1    0.12       0  4998.2    0.07       0
  5027.6    0.12       0  5361.6    0.05       0  5533.4    0.12       0
Bank Sta=4998.2,5027.6
Exp/Cntr=0.3,0.1

Type RM Length L Ch R = 1,10582,537,537,537
BEGIN DESCRIPTION:
COMANCHE CREEK 17.0
END DESCRIPTION:
XS GIS Cut Line= 3
      2855155.69     10158453.12      2855951.75     10159269.00
      2856305.72     10159503.14
#Sta/Elev= 30
  3860.1 1101.67  4008.6 1066.99  4058.0 1058.32  4065.2 1054.85  4095.5 1048.36
  4234.9 1027.82  4390.5 1013.26  4475.2 1007.11  4496.5 1003.65  4581.4 1000.08
  4687.4 1001.65  4782.8  999.14  4870.1  995.61  4926.1  995.32  4963.3  995.41
  4977.5  993.19  4984.5  989.08  5013.6  989.82  5019.9  987.87  5020.4  984.87
  5048.9  984.87  5049.4  987.87  5076.8  995.31  5106.9 1000.72  5164.1 1000.27
  5214.5 1005.51  5234.8 1011.58  5329.5 1029.63  5344.6 1030.30  5424.4 1025.63
#Mann=8,-1,0
  3860.1    0.12       0  4095.5    0.05       0  4782.8    0.12       0
  4870.1    0.05       0  4926.1    0.12       0  5019.9    0.07       0
  5049.4    0.12       0  5234.8    0.05       0
Bank Sta=5019.9,5049.4
Exp/Cntr=0.3,0.1

Type RM Length L Ch R = 1,10045,344,344,344
BEGIN DESCRIPTION:
COMANCHE CREEK 16.0
END DESCRIPTION:
XS GIS Cut Line= 3
      2854621.06     10159130.29      2855886.98     10159788.37
      2856372.52     10159778.36
#Sta/Elev= 30
  3690.5 1042.61  3770.7 1033.05  3875.7 1023.17  3977.5 1011.13  4207.3 1004.49
  4290.1 1004.04  4406.6 1001.02  4460.7 1000.57  4682.5  999.12  4845.3  995.70
  4881.5  993.89  4912.9  987.57  4920.1  990.21  4925.7  987.87  4947.8  989.02
  4969.9  985.96  5002.9  986.52  5010.2  985.08  5010.7  982.08  5039.2  982.08
  5039.7  985.08  5047.1  989.78  5052.7  990.73  5059.4  994.75  5082.3  998.69
  5186.1 1003.96  5255.3 1007.75  5353.3 1012.69  5486.0 1021.93  5602.9 1032.69
#Mann=9,-1,0
  3690.5    0.05       0  4406.6    0.12       0  4460.7    0.05       0
  5010.2    0.05       0  5039.7    0.05       0  5082.3    0.12       0
  5186.1    0.05       0  5255.3    0.12       0  5353.3    0.05       0
Bank Sta=5010.2,5039.7
Exp/Cntr=0.3,0.1

Type RM Length L Ch R = 1,9701,646,646,646
BEGIN DESCRIPTION:
COMANCHE CREEK 15.0
END DESCRIPTION:
XS GIS Cut Line= 3
      2854209.05     10159351.29      2855815.22     10160125.93
      2856454.68     10159969.22
#Sta/Elev= 30
  3403.0 1036.87  3468.1 1028.83  3649.0 1017.03  3948.5 1006.52  4368.6  999.38
  4440.0  998.47  4616.9  998.04  4654.7  998.04  4728.4  997.95  4751.0  996.50
  4764.8  997.53  4818.9  996.96  4869.4  995.08  4960.1  987.36  4982.7  984.10
  4983.2  982.65  4983.7  979.65  5012.3  979.65  5012.8  982.65  5027.9  985.59
  5056.1  987.54  5073.1  990.29  5086.8  994.59  5095.8  993.34  5131.2  996.77
  5191.3  998.88  5262.5 1003.39  5470.5 1007.60  5600.4 1012.44  5844.6 1018.94
#Mann=9,-1,0
  3403.0    0.05       0  4368.6    0.12       0  4440.0    0.05       0
  4616.9    0.12       0  4654.7    0.05       0  4869.4    0.12       0
  4983.2    0.07       0  5012.8    0.12       0  5191.3    0.05       0
Bank Sta=4983.2,5012.8
Exp/Cntr=0.3,0.1

Type RM Length L Ch R = 1,9055,605,605,605
BEGIN DESCRIPTION:
COMANCHE CREEK 14.0
END DESCRIPTION:
XS GIS Cut Line= 3
      2853555.98     10160140.02      2855706.13     10160722.77
      2856780.90     10160521.88
#Sta/Elev= 30
  3051.7 1037.88  3194.3 1029.07  3642.0 1013.11  3828.4 1010.67  4211.8  998.25
  4356.8  999.32  4662.2  990.18  4685.7  990.51  4709.1  986.75  4725.5  991.24
  4879.7  994.96  4919.5  992.79  4968.1  981.45  4979.2  981.27  4979.7  978.27
  5008.3  978.27  5008.8  981.27  5061.4  985.29  5092.5  983.68  5143.0  991.05
  5304.6 1000.68  5482.4 1001.73  5798.7 1009.43  5876.2 1007.52  5894.1 1007.05
  6014.4 1010.37  6180.0 1030.45  6225.0 1037.95  6304.7 1044.38  6372.8 1049.53
#Mann=8,-1,0
  3051.7    0.05       0  4662.2    0.12       0  4979.2    0.05       0
  5008.8    0.12       0  5876.2    0.12       0  5894.1    0.05       0
  6180.0    0.12       0  6304.7    0.05       0
Bank Sta=4979.2,5008.8
Exp/Cntr=0.3,0.1

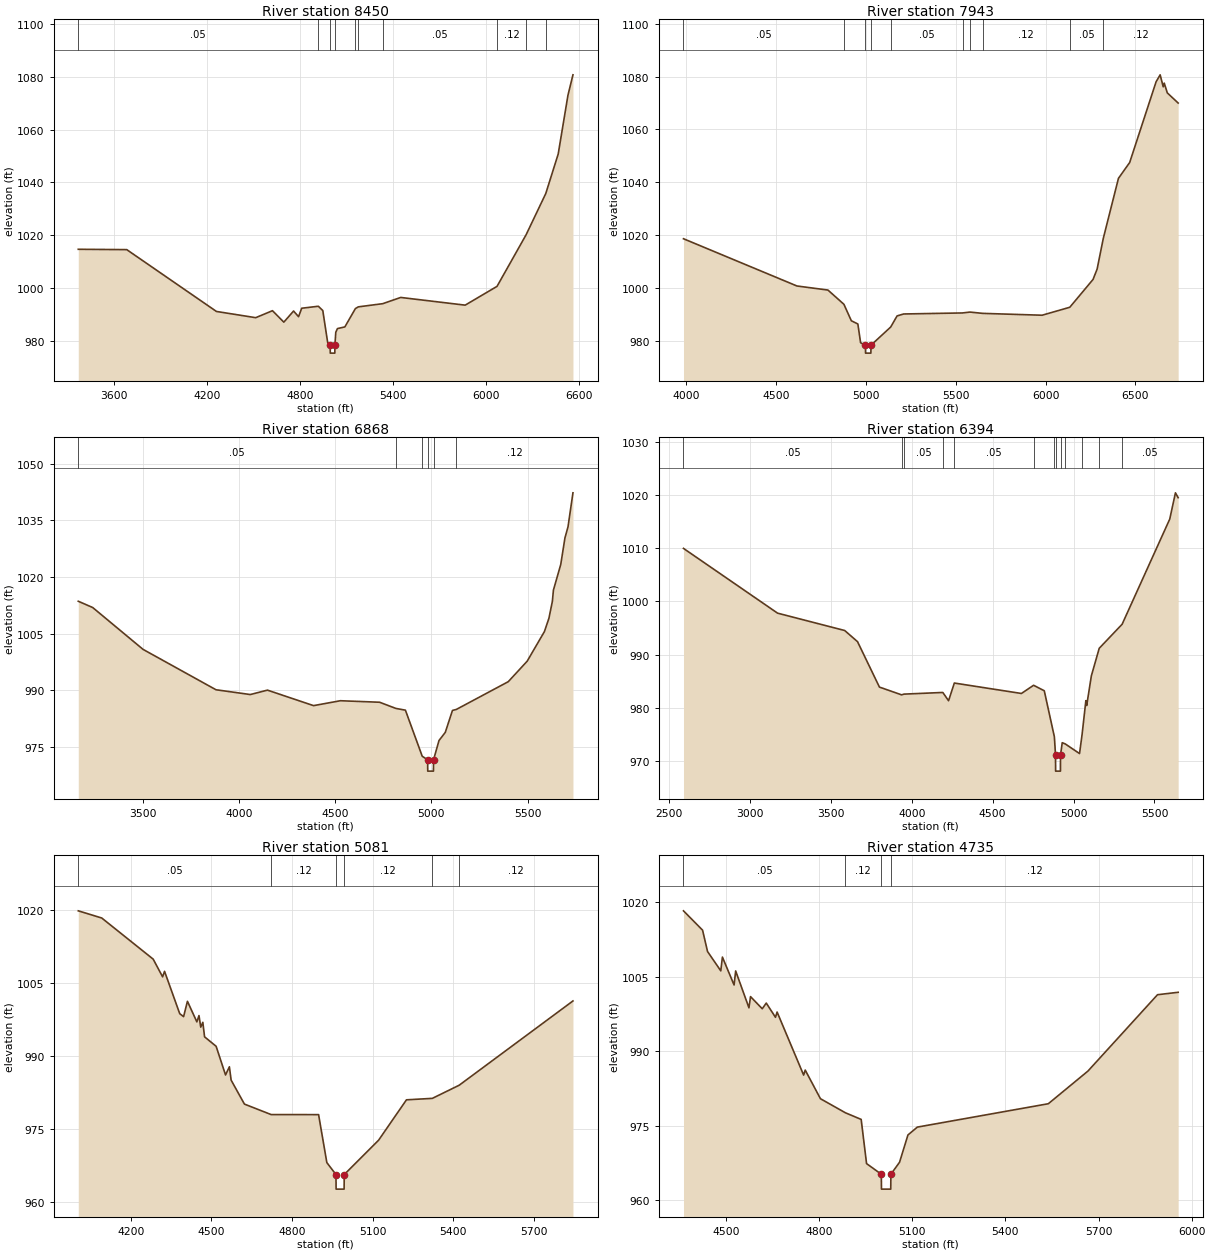
Type RM Length L Ch R = 1,8450,507,507,507
BEGIN DESCRIPTION:
COMANCHE CREEK 13.0
END DESCRIPTION:
XS GIS Cut Line= 3
      2853927.73     10161978.70      2854821.85     10161390.50
      2856846.48     10160762.97
#Sta/Elev= 30
  3371.7 1014.69  3684.3 1014.56  4262.7  991.13  4515.8  988.77  4624.0  991.42
  4697.2  987.08  4760.0  991.29  4792.2  989.15  4812.4  992.35  4919.7  993.10
  4948.5  991.47  4979.9  979.36  4996.1  978.34  4996.6  975.34  5026.1  975.34
  5026.6  978.34  5032.2  983.23  5042.7  984.63  5090.8  985.28  5158.6  992.21
  5177.3  992.87  5335.1  994.08  5451.0  996.44  5866.6  993.52  6072.0 1000.64
  6259.3 1020.17  6386.2 1035.80  6466.5 1050.79  6529.4 1073.07  6561.6 1080.80
#Mann=10,-1,0
  3371.7    0.05       0  4919.7    0.12       0  4996.1    0.07       0
  5026.6    0.12       0  5158.6    0.05       0  5177.3    0.12       0
  5335.1    0.05       0  6072.0    0.12       0  6259.3    0.05       0
  6386.2    0.12       0
Bank Sta=4996.1,5026.6
Exp/Cntr=0.3,0.1

Type RM Length L Ch R = 1,7943,1075,1075,1075
BEGIN DESCRIPTION:
COMANCHE CREEK 12.0
END DESCRIPTION:
XS GIS Cut Line= 3
      2855038.00     10162506.15      2855741.30     10161411.01
      2857047.46     10160783.04
#Sta/Elev= 30
  3986.7 1018.64  4617.6 1000.77  4790.0  999.23  4878.7  993.85  4920.1  987.62
  4956.4  986.39  4971.6  979.30  4998.6  978.37  4999.1  975.37  5028.8  975.37
  5029.3  978.37  5139.1  985.25  5174.4  989.44  5210.8  990.18  5538.6  990.57
  5579.5  990.90  5650.5  990.41  5981.0  989.71  6134.9  992.72  6264.1 1003.24
  6286.7 1007.13  6321.6 1018.91  6405.5 1041.50  6467.8 1047.47  6614.7 1078.01
  6637.3 1080.65  6654.4 1076.12  6660.0 1077.52  6677.1 1073.82  6737.5 1069.98
#Mann=10,-1,0
  3986.7    0.05       0  4878.7    0.12       0  4998.6    0.07       0
  5029.3    0.12       0  5139.1    0.05       0  5538.6    0.12       0
  5579.5    0.05       0  5650.5    0.12       0  6134.9    0.05       0
  6321.6    0.12       0
Bank Sta=4998.6,5029.3
Exp/Cntr=0.3,0.1

Type RM Length L Ch R = 1,6868,474,474,474
BEGIN DESCRIPTION:
COMANCHE CREEK 11.0
END DESCRIPTION:
XS GIS Cut Line= 3
      2855123.37     10162611.67      2856464.70     10161933.47
      2856891.21     10160955.02
#Sta/Elev= 30
  3165.4 1013.55  3240.3 1011.89  3502.1 1000.79  3881.0  990.09  4059.3  988.82
  4148.4  989.99  4388.0  985.88  4527.3  987.18  4731.1  986.78  4815.7  985.14
  4865.2  984.68  4952.6  972.47  4980.7  971.52  4981.2  968.52  5010.9  968.52
  5011.4  971.52  5039.7  976.63  5072.4  978.79  5109.7  984.61  5129.8  984.87
  5399.7  992.23  5497.9  997.66  5587.5 1005.51  5610.9 1009.03  5628.8 1013.52
  5634.3 1016.50  5672.4 1023.31  5694.2 1030.35  5710.0 1033.26  5735.8 1042.29
#Mann=6,-1,0
  3165.4    0.05       0  4815.7    0.12       0  4952.6    0.05       0
  4980.7    0.05       0  5011.4    0.05       0  5129.8    0.12       0
Bank Sta=4980.7,5011.4
Exp/Cntr=0.3,0.1

Type RM Length L Ch R = 1,6394,1313,1313,1313
BEGIN DESCRIPTION:
Mapping XS ff8e7961
END DESCRIPTION:
XS GIS Cut Line= 5
      2855032.98     10163284.82      2856635.51     10162089.20
      2856821.38     10161923.42      2857122.80     10161838.02
      2857483.58     10161497.28
#Sta/Elev= 30
  2588.6 1009.96  3170.3  997.79  3585.2  994.53  3664.4  992.44  3799.9  983.90
  3937.1  982.44  3952.0  982.58  4191.6  982.89  4227.3  981.34  4262.9  984.66
  4677.6  982.70  4752.9  984.24  4818.9  983.21  4881.3  974.57  4888.5  971.11
  4889.0  968.11  4918.8  968.11  4919.3  971.11  4929.9  973.45  4948.7  973.22
  5036.9  971.41  5052.5  974.95  5076.0  981.35  5081.2  980.44  5109.9  986.00
  5158.6  991.19  5300.2  995.71  5594.5 1015.46  5629.8 1020.40  5646.6 1019.49
#Mann=13,-1,0
  2588.6    0.05       0  3937.1    0.12       0  3952.0    0.05       0
  4191.6    0.12       0  4262.9    0.05       0  4752.9    0.12       0
  4881.3    0.05       0  4888.5    0.07       0  4919.3    0.05       0
  4948.7    0.12       0  5052.5    0.05       0  5158.6    0.12       0
  5300.2    0.05       0
Bank Sta=4888.5,4919.3
Exp/Cntr=0.3,0.1

Type RM Length L Ch R = 1,5081,346,346,346
BEGIN DESCRIPTION:
COMANCHE CREEK 10.0
END DESCRIPTION:
XS GIS Cut Line= 3
      2855590.59     10163390.33      2855967.30     10162936.62
      2857191.87     10163199.15
#Sta/Elev= 30
  4004.2 1019.93  4091.6 1018.45  4283.1 1009.98  4318.2 1006.33  4325.5 1007.46
  4382.0  998.74  4396.4  998.13  4410.7 1001.29  4445.8  997.05  4453.7  998.35
  4460.2  995.97  4468.0  996.96  4474.5  993.97  4517.5  992.02  4552.6  986.11
  4566.9  987.80  4573.4  985.05  4622.9  980.11  4722.4  977.95  4899.1  977.94
  4929.8  968.06  4963.8  965.59  4964.3  962.59  4994.1  962.59  4994.6  965.59
  5122.4  972.66  5226.3  980.99  5322.7  981.29  5422.7  984.00  5846.3 1001.36
#Mann=6,-1,0
  4004.2    0.05       0  4722.4    0.12       0  4963.8    0.07       0
  4994.6    0.12       0  5322.7    0.05       0  5422.7    0.12       0
Bank Sta=4963.8,4994.6
Exp/Cntr=0.3,0.1

Type RM Length L Ch R = 1,4735,524,524,524
BEGIN DESCRIPTION:
COMANCHE CREEK 9.0
END DESCRIPTION:
XS GIS Cut Line= 3
      2855635.80     10163465.68      2856092.95     10163360.18
      2857211.96     10163249.79
#Sta/Elev= 30
  4363.0 1018.22  4424.5 1014.33  4440.5 1010.04  4483.2 1006.15  4488.4 1008.92
  4526.0 1003.31  4531.1 1006.13  4573.9  998.72  4579.0 1000.97  4616.7  998.53
  4629.7  999.67  4659.4  996.81  4664.6  997.87  4750.1  985.19  4755.2  986.20
  4804.2  980.44  4884.7  977.61  4935.4  976.28  4952.8  967.39  5000.3  965.26
  5000.8  962.26  5030.7  962.26  5031.2  965.26  5059.0  967.66  5086.1  973.15
  5116.3  974.73  5538.3  979.43  5666.0  986.00  5890.0 1001.35  5956.6 1001.84
#Mann=4,-1,0
  4363.0    0.05       0  4884.7    0.12       0  5000.3    0.07       0
  5031.2    0.12       0
Bank Sta=5000.3,5031.2
Exp/Cntr=0.3,0.1