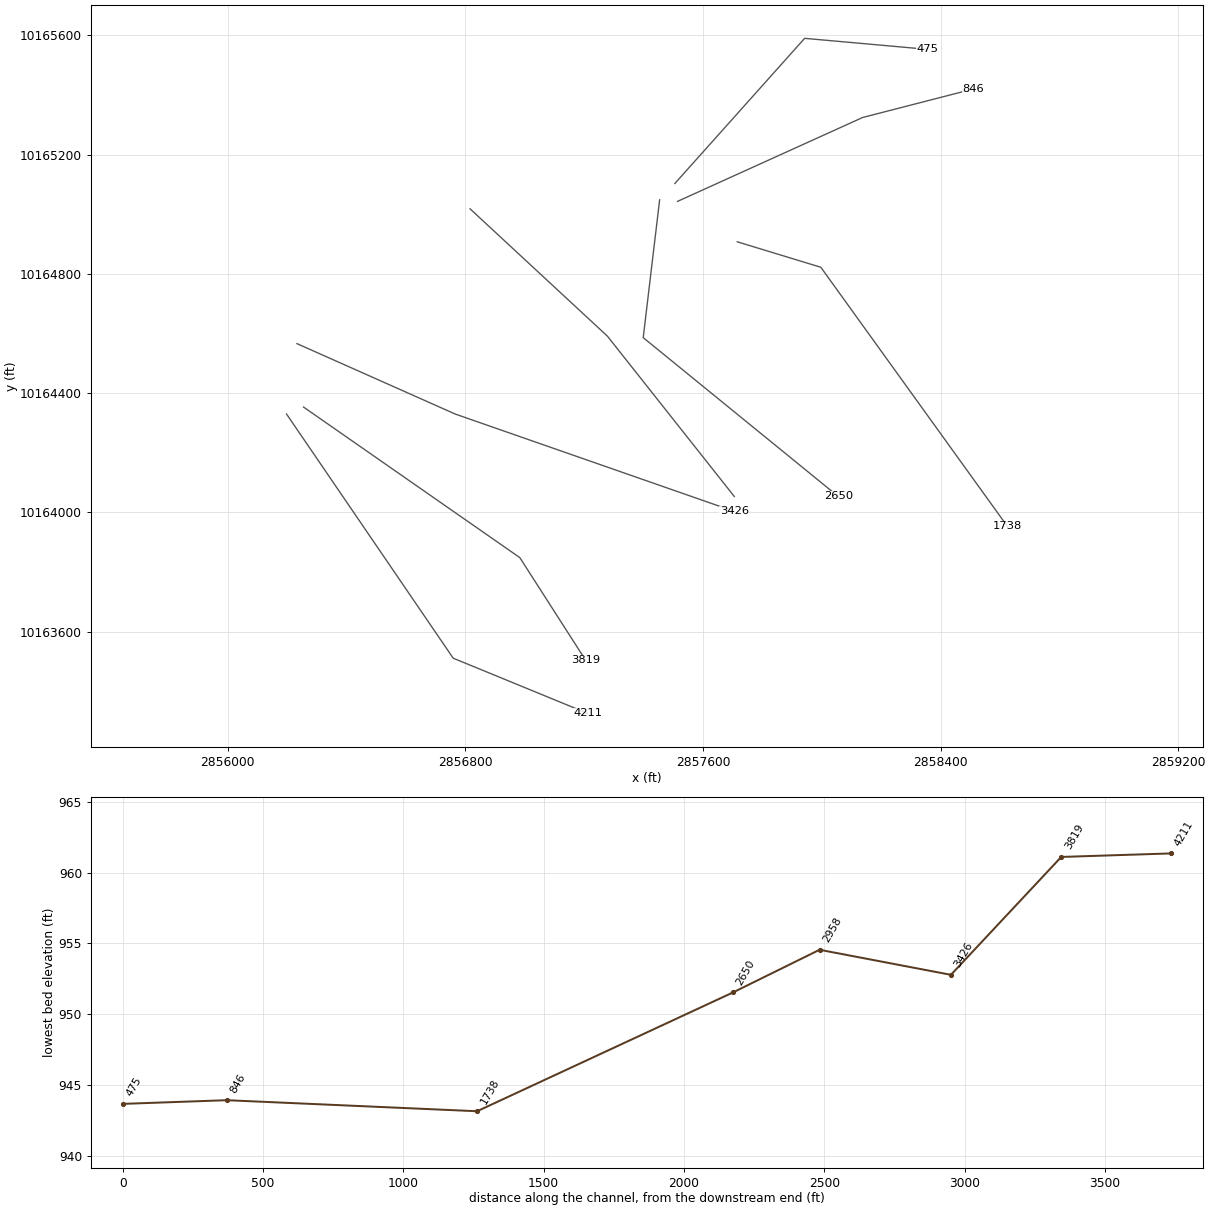
HEC-RAS study COMANCHE CREEK.prj: COMANCHE CREEK Base Level Engineering

--- COMANCHE CREEK.g01 (geometry) --- (continued)

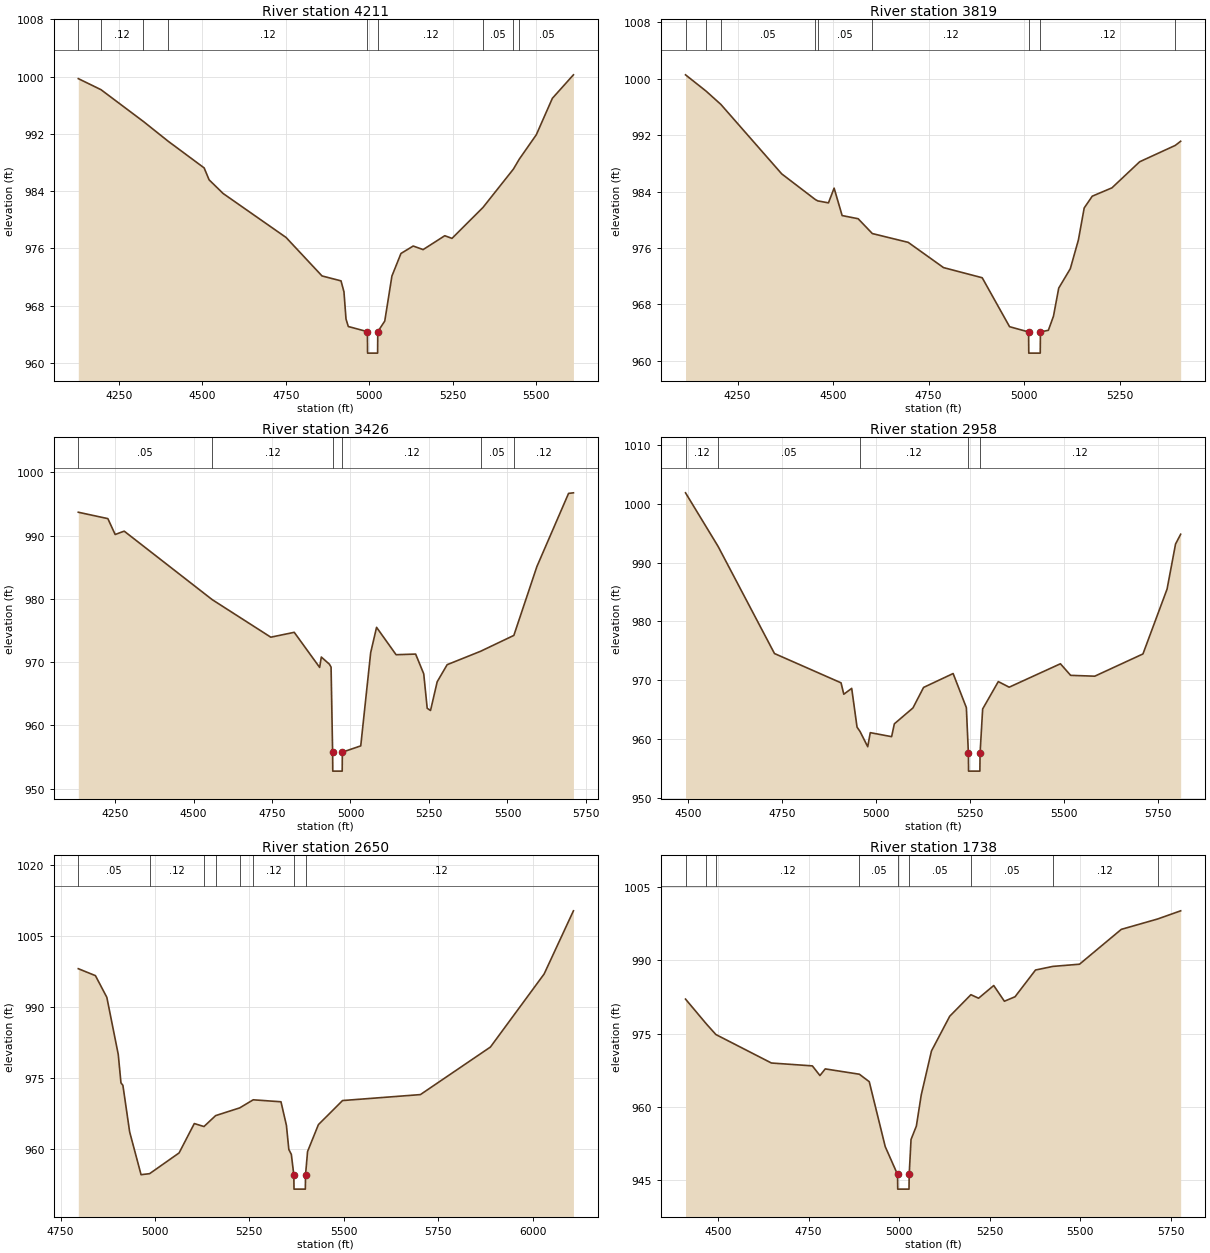
Type RM Length L Ch R = 1,4211,392,392,392
BEGIN DESCRIPTION:
COMANCHE CREEK 8.0
END DESCRIPTION:
XS GIS Cut Line= 3
      2856198.47     10164329.72      2856759.50     10163510.64
      2857212.00     10163325.52
#Sta/Elev= 30
  4129.2  999.72  4197.3  998.17  4324.3  993.72  4397.8  990.98  4505.8  987.24
  4520.7  985.57  4562.7  983.66  4750.9  977.52  4858.5  972.14  4915.4  971.45
  4924.2  969.92  4930.3  966.12  4937.2  965.07  4994.4  964.35  4994.9  961.35
  5024.9  961.35  5025.4  964.35  5046.3  965.83  5067.7  972.12  5094.8  975.28
  5131.4  976.32  5161.1  975.82  5225.9  977.76  5247.5  977.39  5340.2  981.71
  5431.2  987.07  5448.8  988.46  5499.9  991.88  5547.9  996.97  5610.9 1000.25
#Mann=9,-1,0
  4129.2    0.05       0  4197.3    0.12       0  4324.3    0.05       0
  4397.8    0.12       0  4994.4    0.07       0  5025.4    0.12       0
  5340.2    0.05       0  5431.2    0.12       0  5448.8    0.05       0
Bank Sta=4994.4,5025.4
Exp/Cntr=0.3,0.1

Type RM Length L Ch R = 1,3819,393,393,393
BEGIN DESCRIPTION:
COMANCHE CREEK 7.0
END DESCRIPTION:
XS GIS Cut Line= 3
      2856255.70     10164353.10      2856983.75     10163848.00
      2857205.67     10163503.13
#Sta/Elev= 30
  4113.9 1000.57  4167.5  998.27  4206.3  996.38  4365.8  986.52  4454.0  982.87
  4460.3  982.69  4488.1  982.41  4502.9  984.50  4523.9  980.61  4565.8  980.16
  4602.9  978.06  4696.8  976.81  4789.3  973.23  4890.6  971.79  4962.2  964.85
  5012.0  964.10  5012.5  961.10  5042.5  961.10  5043.0  964.10  5063.8  964.34
  5077.2  966.35  5090.9  970.32  5121.2  973.07  5142.4  977.15  5157.6  981.69
  5178.7  983.36  5230.2  984.54  5302.8  988.24  5396.0  990.56  5410.1  991.15
#Mann=9,-1,0
  4113.9    0.05       0  4167.5    0.12       0  4206.3    0.05       0
  4454.0    0.12       0  4460.3    0.05       0  4602.9    0.12       0
  5012.0    0.07       0  5043.0    0.12       0  5396.0    0.05       0
Bank Sta=5012,5043
Exp/Cntr=0.3,0.1

Type RM Length L Ch R = 1,3426,468,468,468
BEGIN DESCRIPTION:
COMANCHE CREEK 6.0
END DESCRIPTION:
XS GIS Cut Line= 3
      2856233.60     10164565.86      2856766.12     10164329.74
      2857705.65     10164003.12
#Sta/Elev= 30
  4133.0  993.71  4227.2  992.70  4250.5  990.19  4279.2  990.72  4559.8  979.88
  4746.2  973.95  4820.9  974.72  4901.8  969.17  4907.1  970.81  4932.9  969.68
  4938.2  969.21  4943.1  955.77  4943.6  952.77  4973.6  952.77  4974.1  955.77
  5032.7  956.76  5064.4  971.52  5083.1  975.51  5145.3  971.18  5207.6  971.28
  5233.4  968.15  5244.4  962.71  5255.0  962.36  5276.2  966.90  5307.9  969.60
  5414.3  971.72  5520.4  974.23  5593.8  985.12  5694.7  996.69  5710.2  996.78
#Mann=6,-1,0
  4133.0    0.05       0  4559.8    0.12       0  4943.1    0.07       0
  4974.1    0.12       0  5414.3    0.05       0  5520.4    0.12       0
Bank Sta=4943.1,4974.1
Exp/Cntr=0.3,0.1

Type RM Length L Ch R = 1,2958,308,308,308
BEGIN DESCRIPTION:
COMANCHE CREEK 5.0
END DESCRIPTION:
XS GIS Cut Line= 3
      2856816.36     10165017.98      2857278.53     10164590.97
      2857705.69     10164053.10
#Sta/Elev= 30
  4493.6 1001.85  4580.3  992.73  4730.1  974.53  4907.0  969.55  4914.3  967.61
  4935.3  968.61  4949.5  962.03  4957.8  961.24  4977.9  958.69  4984.7  961.08
  5041.4  960.40  5048.7  962.58  5098.1  965.28  5126.4  968.77  5204.9  971.13
  5240.1  965.33  5245.5  957.54  5246.0  954.54  5276.0  954.54  5276.5  957.54
  5283.4  965.11  5325.0  969.76  5353.9  968.81  5490.1  972.79  5517.3  970.82
  5581.4  970.68  5709.5  974.46  5773.6  985.49  5796.1  993.14  5809.7  994.81
#Mann=5,-1,0
  4493.6    0.12       0  4580.3    0.05       0  4957.8    0.12       0
  5245.5    0.07       0  5276.5    0.12       0
Bank Sta=5245.5,5276.5
Exp/Cntr=0.3,0.1

Type RM Length L Ch R = 1,2650,912,912,912
BEGIN DESCRIPTION:
COMANCHE CREEK 4.0
END DESCRIPTION:
XS GIS Cut Line= 3
      2857454.37     10165048.17      2857399.10     10164585.95
      2858055.69     10164053.11
#Sta/Elev= 30
  4797.1  998.12  4842.5  996.65  4872.7  992.06  4902.9  980.00  4910.1  973.99
  4915.2  973.47  4933.1  963.62  4963.3  954.58  4986.0  954.80  5064.0  959.18
  5104.3  965.39  5129.9  964.76  5160.8  967.07  5224.5  968.70  5260.3  970.41
  5333.8  969.99  5348.2  965.01  5354.6  959.90  5361.2  958.88  5367.8  954.53
  5368.3  951.53  5398.3  951.53  5398.8  954.53  5404.2  959.48  5432.9  965.16
  5496.8  970.25  5703.0  971.51  5888.4  981.56  6030.6  997.00  6108.2 1010.35
#Mann=8,-1,0
  4797.1    0.05       0  4986.0    0.12       0  5129.9    0.05       0
  5160.8    0.12       0  5224.5    0.05       0  5260.3    0.12       0
  5367.8    0.07       0  5398.8    0.12       0
Bank Sta=5367.8,5398.8
Exp/Cntr=0.3,0.1

Type RM Length L Ch R = 1,1738,892,892,892
BEGIN DESCRIPTION:
COMANCHE CREEK 3.0
END DESCRIPTION:
XS GIS Cut Line= 3
      2857715.56     10164907.47      2857996.91     10164822.06
      2858624.90     10163952.93
#Sta/Elev= 30
  4410.5  982.08  4467.9  977.00  4494.4  974.81  4647.5  968.98  4760.5  968.39
  4781.4  966.41  4796.1  967.77  4890.2  966.68  4917.5  965.15  4961.6  951.84
  4995.6  946.13  4996.1  943.13  5027.2  943.13  5027.7  946.13  5032.8  953.31
  5047.5  956.05  5061.0  962.45  5089.2  971.45  5139.5  978.56  5198.0  982.98
  5219.2  982.26  5261.0  984.86  5290.4  981.64  5319.8  982.56  5376.3  988.04
  5424.3  988.78  5497.7  989.23  5613.0  996.37  5713.0  998.49  5776.8 1000.17
#Mann=9,-1,0
  4410.5    0.12       0  4467.9    0.05       0  4494.4    0.12       0
  4890.2    0.05       0  4995.6    0.05       0  5027.7    0.05       0
  5198.0    0.05       0  5424.3    0.12       0  5713.0    0.05       0
Bank Sta=4995.6,5027.7
Exp/Cntr=0.3,0.1

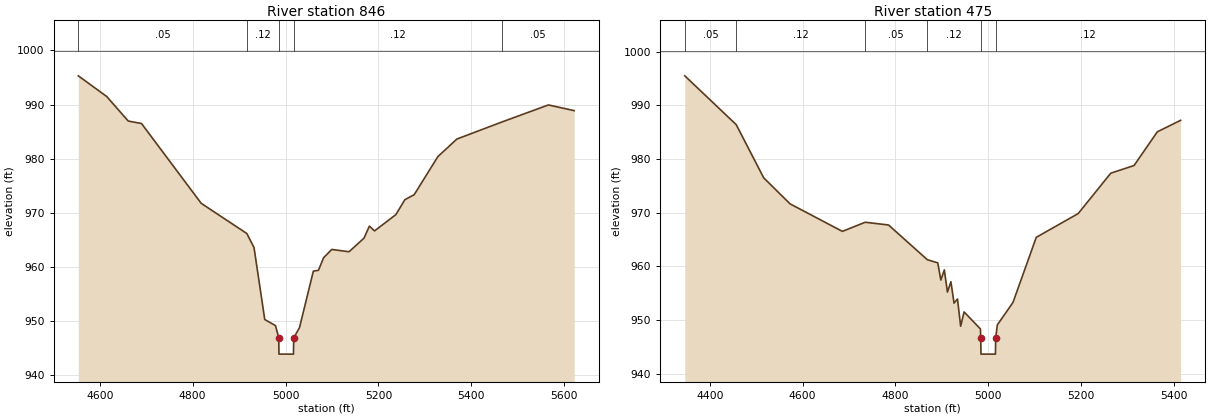
Type RM Length L Ch R = 1,846,371,371,371
BEGIN DESCRIPTION:
COMANCHE CREEK 2.0
END DESCRIPTION:
XS GIS Cut Line= 3
      2857514.64     10165043.10      2858137.58     10165324.42
      2858509.30     10165419.87
#Sta/Elev= 30
  4554.0  995.32  4615.1  991.50  4661.4  986.97  4690.0  986.51  4818.5  971.77
  4916.7  966.19  4932.2  963.60  4955.3  950.30  4978.4  949.18  4985.4  946.91
  4985.9  943.91  5017.1  943.91  5017.6  946.91  5030.1  948.81  5059.9  959.24
  5070.9  959.40  5081.9  961.71  5099.5  963.25  5136.7  962.82  5168.9  965.33
  5180.6  967.56  5191.6  966.67  5237.5  969.68  5256.9  972.44  5276.9  973.36
  5328.0  980.40  5368.8  983.64  5465.4  986.78  5565.9  989.94  5621.3  988.89
#Mann=5,-1,0
  4554.0    0.05       0  4916.7    0.12       0  4985.4    0.07       0
  5017.6    0.12       0  5465.4    0.05       0
Bank Sta=4985.4,5017.6
Exp/Cntr=0.3,0.1

Type RM Length L Ch R = 1,475,0,0,0
BEGIN DESCRIPTION:
COMANCHE CREEK 1.0
END DESCRIPTION:
XS GIS Cut Line= 3
      2857505.70     10165103.12      2857942.50     10165590.00
      2858355.66     10165553.11
#Sta/Elev= 30
  4345.9  995.50  4456.8  986.40  4516.0  976.50  4572.8  971.65  4685.6  966.52
  4734.9  968.22  4785.1  967.71  4868.8  961.24  4891.2  960.66  4897.9  957.45
  4905.4  959.35  4912.1  955.21  4919.6  957.14  4926.3  953.15  4933.8  953.92
  4940.6  948.85  4948.0  951.51  4983.2  948.35  4983.9  946.65  4984.4  943.65
  5015.6  943.65  5016.1  946.65  5019.7  949.10  5053.4  953.28  5103.6  965.41
  5194.0  969.84  5264.2  977.36  5314.4  978.79  5364.6  985.07  5414.8  987.21
#Mann=6,-1,0
  4345.9    0.05       0  4456.8    0.12       0  4734.9    0.05       0
  4868.8    0.12       0  4983.9    0.07       0  5016.1    0.12       0
Bank Sta=4983.9,5016.1
Exp/Cntr=0.3,0.1

Chan Stop Cuts=-1