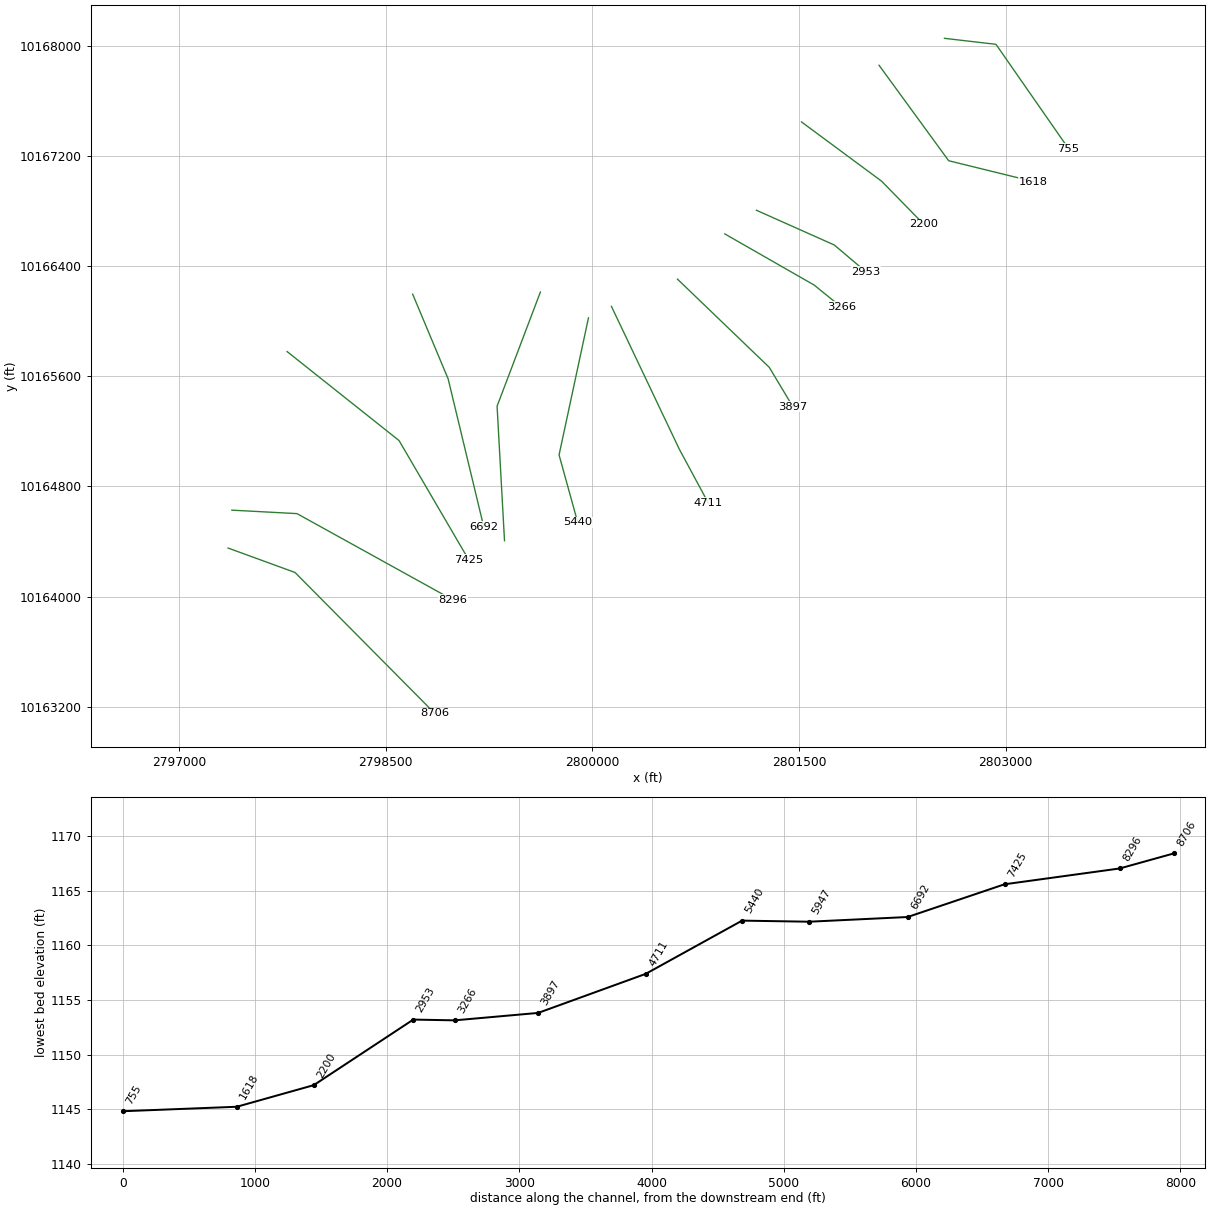
HEC-RAS study CRABAPPLE CREEK.prj: CRABAPPLE CREEK Base Level Engineering

--- CRABAPPLE CREEK.g01 (geometry) --- (continued)

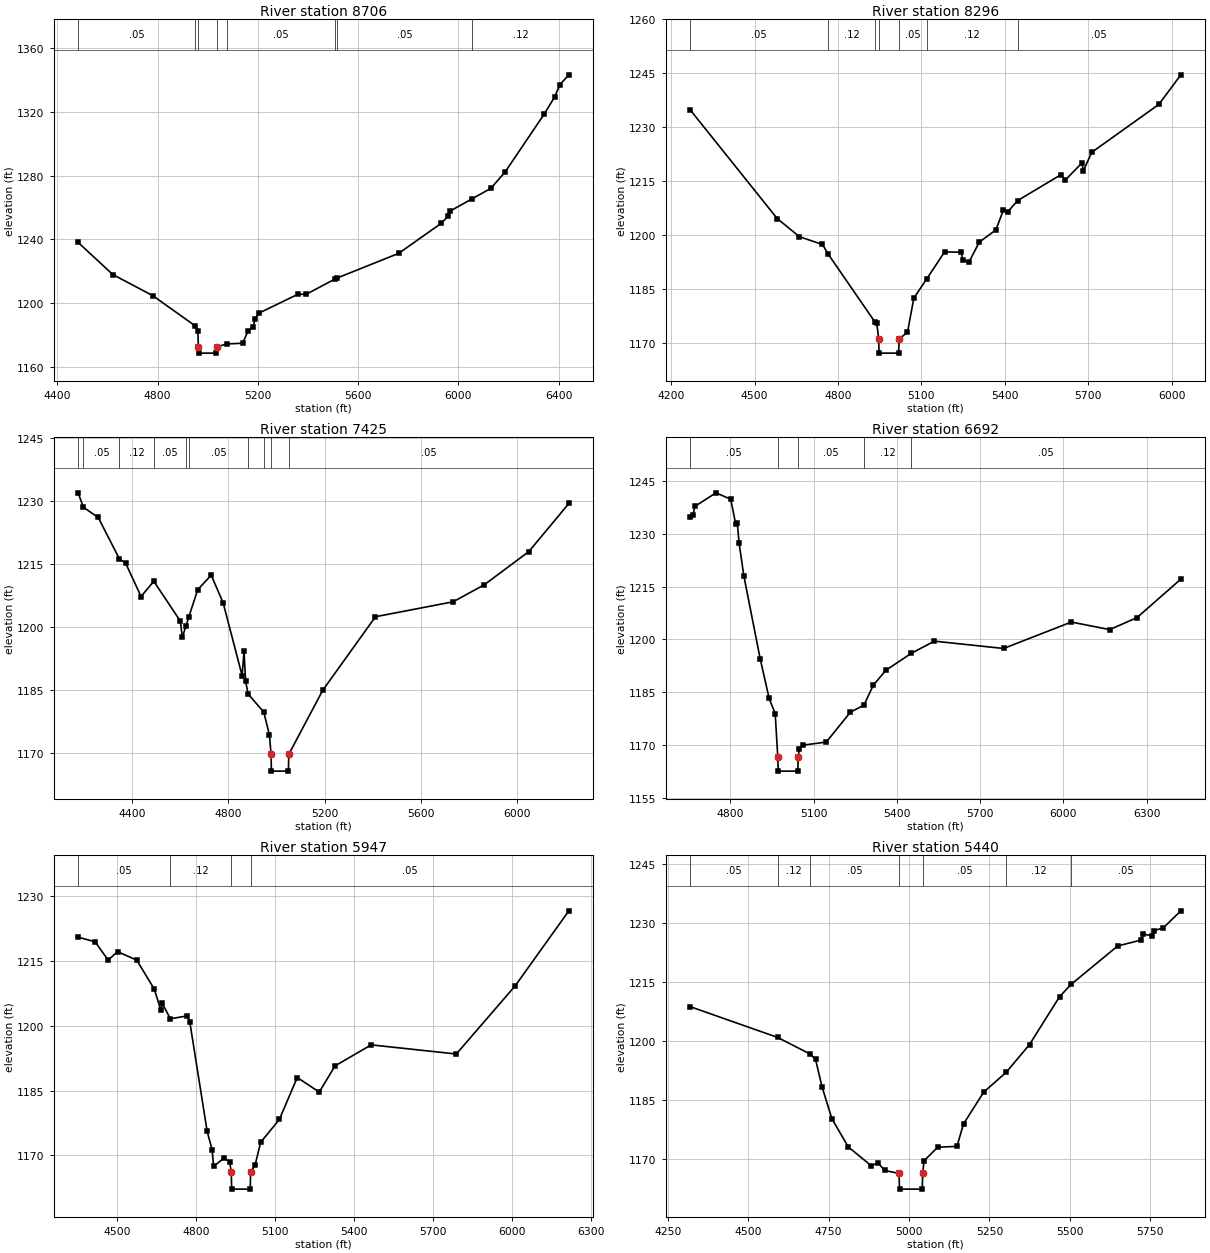
Type RM Length L Ch R = 1,8706,410,410,410
BEGIN DESCRIPTION:
CRABAPPLE CREEK 13.0
END DESCRIPTION:
XS GIS Cut Line= 3
      2797355.65     10164353.13      2797841.25     10164176.00
      2798855.67     10163153.12
#Sta/Elev= 30
  4483.1 1238.06  4621.5 1217.85  4781.2 1204.56  4950.0 1185.62  4960.7 1182.31
  4962.9 1172.44  4964.4 1168.44  5034.9 1168.44  5036.4 1172.44  5076.7 1174.20
  5139.5 1174.67  5160.7 1182.19  5182.0 1185.16  5189.0 1190.06  5203.1 1193.48
  5358.7 1205.37  5394.1 1205.53  5506.0 1214.87  5517.8 1215.75  5761.8 1231.16
  5931.5 1250.05  5959.8 1254.70  5966.8 1257.73  6055.1 1265.49  6129.5 1272.04
  6186.1 1282.26  6341.6 1318.55  6384.1 1329.56  6405.3 1337.31  6440.6 1343.40
#Mann=8,-1,0
  4483.1    0.05       0  4950.0    0.12       0  4962.9    0.07       0
  5036.4    0.12       0  5076.7    0.05       0  5506.0    0.12       0
  5517.8    0.05       0  6055.1    0.12       0
Bank Sta=4962.9,5036.4
Exp/Cntr=0.3,0.1

Type RM Length L Ch R = 1,8296,871,871,871
BEGIN DESCRIPTION:
CRABAPPLE CREEK 12.0
END DESCRIPTION:
XS GIS Cut Line= 3
      2797382.97     10164628.23      2797855.68     10164603.11
      2798986.23     10163977.67
#Sta/Elev= 30
  4268.1 1234.80  4581.3 1204.53  4661.4 1199.46  4744.3 1197.30  4764.4 1194.67
  4933.6 1175.65  4939.6 1175.35  4946.4 1171.06  4947.9 1167.06  5018.4 1167.06
  5019.9 1171.06  5050.0 1172.83  5072.9 1182.38  5119.4 1187.74  5183.6 1195.23
  5243.1 1195.15  5248.8 1192.99  5270.6 1192.31  5308.4 1197.96  5367.9 1201.35
  5395.4 1206.93  5411.5 1206.47  5446.4 1209.52  5601.6 1216.70  5617.6 1215.22
  5677.2 1219.96  5682.9 1217.84  5712.9 1222.95  5954.3 1236.30  6033.5 1244.52
#Mann=7,-1,0
  4268.1    0.05       0  4764.4    0.12       0  4933.6    0.05       0
  4946.4    0.05       0  5019.9    0.05       0  5119.4    0.12       0
  5446.4    0.05       0
Bank Sta=4946.4,5019.9
Exp/Cntr=0.3,0.1

Type RM Length L Ch R = 1,7425,733,733,733
BEGIN DESCRIPTION:
CRABAPPLE CREEK 11.0
END DESCRIPTION:
XS GIS Cut Line= 3
      2797784.01     10165779.25      2798596.47     10165133.44
      2799101.16     10164269.75
#Sta/Elev= 30
  4175.7 1231.94  4197.7 1228.51  4259.4 1226.06  4347.5 1216.18  4373.1 1215.19
  4437.2 1207.23  4490.3 1210.86  4600.6 1201.35  4608.6 1197.50  4624.2 1200.28
  4634.8 1202.23  4672.7 1208.86  4728.7 1212.32  4778.4 1205.68  4856.9 1188.38
  4864.9 1194.16  4871.3 1187.04  4882.1 1183.98  4946.9 1179.66  4970.6 1174.20
  4977.1 1169.61  4978.6 1165.61  5049.2 1165.61  5050.7 1169.61  5191.7 1184.87
  5410.8 1202.41  5733.3 1205.97  5862.5 1210.02  6047.9 1217.95  6213.9 1229.41
#Mann=10,-1,0
  4175.7    0.12       0  4197.7    0.05       0  4347.5    0.12       0
  4490.3    0.05       0  4624.2    0.12       0  4634.8    0.05       0
  4882.1    0.12       0  4946.9    0.05       0  4977.1    0.05       0
  5050.7    0.05       0
Bank Sta=4977.1,5050.7
Exp/Cntr=0.3,0.1

Type RM Length L Ch R = 1,6692,745,745,745
BEGIN DESCRIPTION:
CRABAPPLE CREEK 10.0
END DESCRIPTION:
XS GIS Cut Line= 3
      2798695.41     10166195.99      2798952.88     10165580.98
      2799210.87     10164509.22
#Sta/Elev= 30
  4654.4 1234.88  4665.5 1235.29  4670.9 1237.76  4747.7 1241.64  4800.7 1239.83
  4819.1 1232.67  4824.5 1233.14  4831.0 1227.33  4848.3 1217.98  4906.9 1194.56
  4939.4 1183.26  4961.1 1178.95  4970.5 1166.61  4972.0 1162.61  5042.6 1162.61
  5044.1 1166.61  5047.8 1168.80  5060.3 1169.97  5145.4 1170.87  5232.1 1179.34
  5281.1 1181.35  5314.4 1186.96  5360.1 1191.25  5451.5 1196.05  5534.9 1199.52
  5784.4 1197.44  6028.6 1204.94  6166.9 1202.80  6265.2 1206.20  6423.5 1217.14
#Mann=5,-1,0
  4654.4    0.05       0  4970.5    0.03       0  5044.1    0.05       0
  5281.1    0.12       0  5451.5    0.05       0
Bank Sta=4970.5,5044.1
Exp/Cntr=0.3,0.1

Type RM Length L Ch R = 1,5947,507,507,507
BEGIN DESCRIPTION:
CRABAPPLE CREEK 9.0
END DESCRIPTION:
XS GIS Cut Line= 3
      2799622.52     10166211.58      2799308.05     10165382.73
      2799361.99     10164406.21
#Sta/Elev= 30
  4352.3 1220.54  4417.0 1219.45  4466.6 1215.22  4502.1 1217.17  4575.3 1215.21
  4642.1 1208.46  4666.9 1203.57  4672.2 1205.18  4703.0 1201.63  4767.8 1202.31
  4776.7 1200.90  4842.7 1175.54  4861.8 1171.22  4867.1 1167.44  4906.8 1169.39
  4928.2 1168.44  4934.2 1166.18  4935.7 1162.18  5006.3 1162.18  5007.8 1166.18
  5024.5 1167.69  5045.9 1173.02  5117.0 1178.31  5184.9 1188.03  5268.5 1184.66
  5328.6 1190.72  5465.8 1195.59  5789.3 1193.47  6013.2 1209.28  6216.8 1226.63
#Mann=4,-1,0
  4352.3    0.05       0  4703.0    0.12       0  4934.2    0.05       0
  5007.8    0.05       0
Bank Sta=4934.2,5007.8
Exp/Cntr=0.3,0.1

Type RM Length L Ch R = 1,5440,729,729,729
BEGIN DESCRIPTION:
CRABAPPLE CREEK 8.0
END DESCRIPTION:
XS GIS Cut Line= 3
      2799971.46     10166024.03      2799757.93     10165029.28
      2799893.35     10164539.67
#Sta/Elev= 30
  4319.6 1208.74  4591.4 1200.91  4692.9 1196.66  4709.4 1195.33  4729.7 1188.31
  4760.3 1180.19  4811.5 1173.00  4883.1 1168.21  4903.5 1169.03  4924.0 1167.03
  4969.0 1166.28  4970.5 1162.28  5041.1 1162.28  5042.6 1166.28  5046.7 1169.49
  5089.2 1172.95  5149.0 1173.17  5169.4 1178.88  5232.3 1186.99  5301.7 1191.99
  5374.5 1199.09  5467.9 1211.26  5503.5 1214.38  5648.5 1224.18  5722.3 1225.71
  5727.5 1227.15  5756.6 1226.82  5761.8 1228.12  5789.6 1228.75  5845.0 1233.13
#Mann=7,-1,0
  4319.6    0.05       0  4591.4    0.12       0  4692.9    0.05       0
  4969.0    0.05       0  5042.6    0.05       0  5301.7    0.12       0
  5503.5    0.05       0
Bank Sta=4969,5042.6
Exp/Cntr=0.3,0.1

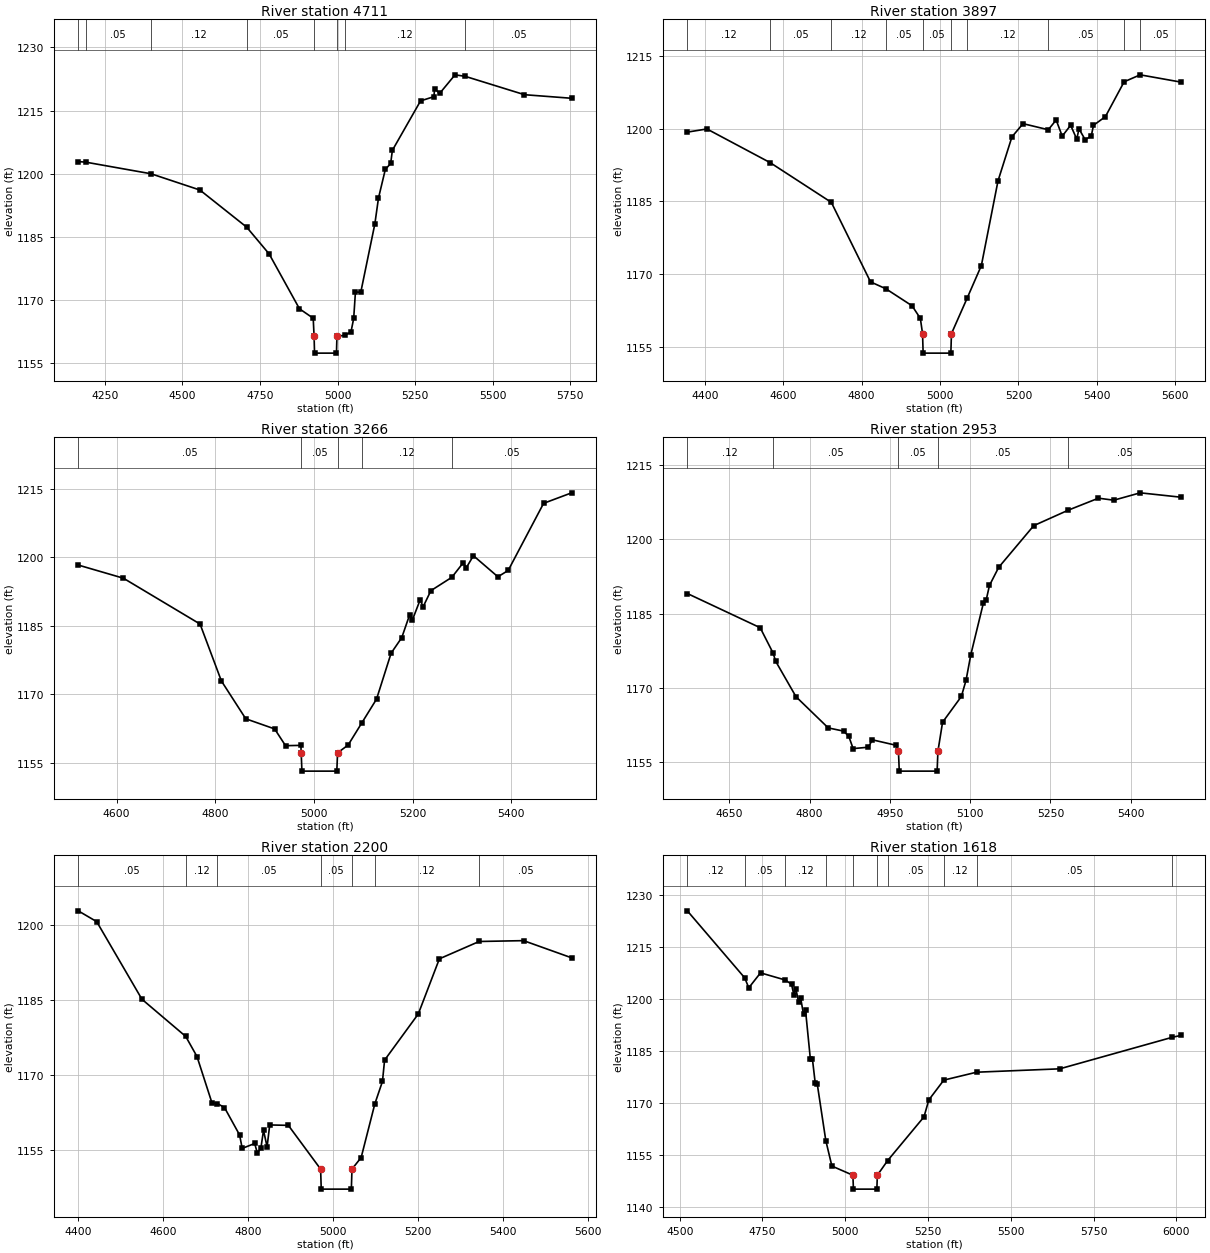
Type RM Length L Ch R = 1,4711,814,814,814
BEGIN DESCRIPTION:
CRABAPPLE CREEK 7.0
END DESCRIPTION:
XS GIS Cut Line= 3
      2800138.14     10166107.41      2800630.24     10165071.81
      2800840.97     10164680.86
#Sta/Elev= 30
  4164.1 1202.89  4187.6 1202.77  4398.9 1200.00  4556.4 1196.14  4707.2 1187.32
  4779.6 1180.96  4877.4 1167.93  4921.7 1165.69  4924.5 1161.40  4926.0 1157.40
  4996.7 1157.40  4998.2 1161.40  5024.8 1161.65  5043.5 1162.45  5052.2 1165.65
  5057.8 1171.93  5075.0 1171.85  5120.4 1188.08  5132.1 1194.22  5154.2 1201.04
  5171.4 1202.44  5176.9 1205.57  5267.8 1217.31  5310.7 1218.31  5313.2 1220.20
  5329.5 1219.10  5378.9 1223.50  5411.8 1223.14  5602.8 1218.78  5754.8 1217.93
#Mann=8,-1,0
  4164.1    0.12       0  4187.6    0.05       0  4398.9    0.12       0
  4707.2    0.05       0  4924.5    0.05       0  4998.2    0.05       0
  5024.8    0.12       0  5411.8    0.05       0
Bank Sta=4924.5,4998.2
Exp/Cntr=0.3,0.1

Type RM Length L Ch R = 1,3897,631,631,631
BEGIN DESCRIPTION:
CRABAPPLE CREEK 6.0
END DESCRIPTION:
XS GIS Cut Line= 3
      2800617.30     10166305.32      2801283.97     10165664.69
      2801455.82     10165378.28
#Sta/Elev= 30
  4355.3 1199.26  4405.3 1199.91  4566.5 1192.99  4722.6 1184.82  4822.6 1168.47
  4861.8 1167.05  4928.6 1163.55  4949.7 1160.96  4955.3 1157.82  4956.8 1153.82
  5027.5 1153.82  5029.0 1157.82  5069.2 1165.15  5105.3 1171.82  5147.8 1189.24
  5183.3 1198.28  5211.6 1201.00  5276.0 1199.75  5296.1 1201.75  5311.6 1198.43
  5333.0 1200.67  5348.6 1197.83  5354.4 1199.93  5369.9 1197.73  5385.5 1198.40
  5391.3 1200.66  5421.7 1202.44  5469.5 1209.61  5510.4 1211.04  5613.9 1209.55
#Mann=10,-1,0
  4355.3    0.12       0  4566.5    0.05       0  4722.6    0.12       0
  4861.8    0.05       0  4955.3    0.05       0  5029.0    0.05       0
  5069.2    0.12       0  5276.0    0.05       0  5469.5    0.12       0
  5510.4    0.05       0
Bank Sta=4955.3,5029
Exp/Cntr=0.3,0.1

Type RM Length L Ch R = 1,3266,313,313,313
BEGIN DESCRIPTION:
CRABAPPLE CREEK 5.0
END DESCRIPTION:
XS GIS Cut Line= 3
      2800961.07     10166633.44      2801610.04     10166261.95
      2801805.70     10166103.10
#Sta/Elev= 30
  4522.3 1198.26  4613.8 1195.38  4769.2 1185.34  4812.4 1172.88  4861.8 1164.60
  4920.3 1162.38  4942.4 1158.71  4973.5 1158.78  4974.1 1157.14  4975.6 1153.14
  5046.3 1153.14  5047.8 1157.14  5069.2 1158.85  5096.9 1163.69  5126.8 1168.91
  5156.3 1178.96  5177.9 1182.37  5193.7 1187.32  5199.5 1186.25  5215.3 1190.68
  5221.1 1189.10  5236.9 1192.65  5279.4 1195.58  5302.3 1198.74  5308.7 1197.68
  5323.1 1200.30  5372.7 1195.69  5393.5 1197.07  5465.3 1211.77  5522.1 1214.07
#Mann=5,-1,0
  4522.3    0.05       0  4974.1    0.05       0  5047.8    0.05       0
  5096.9    0.12       0  5279.4    0.05       0
Bank Sta=4974.1,5047.8
Exp/Cntr=0.3,0.1

Type RM Length L Ch R = 1,2953,753,753,753
BEGIN DESCRIPTION:
CRABAPPLE CREEK 4.0
END DESCRIPTION:
XS GIS Cut Line= 3
      2801190.25     10166805.31      2801755.68     10166553.11
      2801986.71     10166357.73
#Sta/Elev= 30
  4571.7 1189.08  4707.8 1182.17  4732.1 1177.01  4736.5 1175.44  4774.7 1168.24
  4834.9 1161.94  4863.6 1161.29  4873.3 1160.24  4881.4 1157.76  4910.1 1158.04
  4917.1 1159.54  4962.0 1158.42  4966.1 1157.21  4967.6 1153.21  5038.3 1153.21
  5039.8 1157.21  5048.5 1163.08  5083.6 1168.29  5092.3 1171.54  5101.3 1176.75
  5124.6 1187.09  5130.0 1187.78  5136.1 1190.71  5153.3 1194.36  5218.8 1202.78
  5283.3 1205.91  5339.7 1208.33  5368.3 1207.92  5417.7 1209.41  5493.4 1208.53
#Mann=5,-1,0
  4571.7    0.12       0  4732.1    0.05       0  4966.1    0.05       0
  5039.8    0.05       0  5283.3    0.05       0
Bank Sta=4966.1,5039.8
Exp/Cntr=0.3,0.1

Type RM Length L Ch R = 1,2200,582,582,582
BEGIN DESCRIPTION:
CRABAPPLE CREEK 3.0
END DESCRIPTION:
XS GIS Cut Line= 3
      2801518.33     10167445.96      2802098.82     10167016.54
      2802405.69     10166703.11
#Sta/Elev= 30
  4401.2 1202.75  4444.7 1200.59  4551.1 1185.10  4654.1 1177.68  4680.6 1173.67
  4716.1 1164.34  4728.8 1164.28  4745.3 1163.48  4780.8 1158.02  4787.0 1155.33
  4816.3 1156.31  4822.5 1154.43  4830.9 1155.37  4837.1 1158.94  4845.5 1155.64
  4851.7 1160.01  4895.5 1159.93  4971.4 1151.20  4972.9 1147.20  5043.7 1147.20
  5045.2 1151.20  5066.8 1153.51  5099.0 1164.23  5116.9 1168.70  5121.9 1172.95
  5201.2 1182.17  5250.8 1193.17  5344.3 1196.63  5448.8 1196.80  5561.9 1193.37
#Mann=7,-1,0
  4401.2    0.05       0  4654.1    0.12       0  4728.8    0.05       0
  4971.4    0.05       0  5045.2    0.05       0  5099.0    0.12       0
  5344.3    0.05       0
Bank Sta=4971.4,5045.2
Exp/Cntr=0.3,0.1

Type RM Length L Ch R = 1,1618,863,863,863
BEGIN DESCRIPTION:
CRABAPPLE CREEK 2.0
END DESCRIPTION:
XS GIS Cut Line= 3
      2802080.87     10167857.38      2802586.05     10167164.69
      2803200.63     10167013.65
#Sta/Elev= 30
  4523.0 1225.31  4696.3 1206.02  4708.6 1203.16  4744.1 1207.46  4818.8 1205.40
  4837.7 1204.19  4844.5 1201.21  4850.7 1202.87  4859.2 1199.09  4865.4 1200.10
  4873.9 1195.57  4880.0 1196.68  4894.7 1182.56  4900.9 1182.60  4909.4 1175.63
  4915.6 1175.36  4941.2 1159.21  4959.6 1151.86  5023.1 1149.22  5024.6 1145.22
  5095.4 1145.22  5096.9 1149.22  5128.0 1153.44  5237.7 1166.01  5252.4 1170.90
  5297.6 1176.59  5396.7 1178.87  5647.7 1179.84  5988.2 1188.93  6013.2 1189.45
#Mann=10,-1,0
  4523.0    0.12       0  4696.3    0.05       0  4818.8    0.12       0
  4941.2    0.05       0  5023.1    0.05       0  5096.9    0.05       0
  5128.0    0.05       0  5297.6    0.12       0  5396.7    0.05       0
  5988.2    0.12       0
Bank Sta=5023.1,5096.9
Exp/Cntr=0.3,0.1

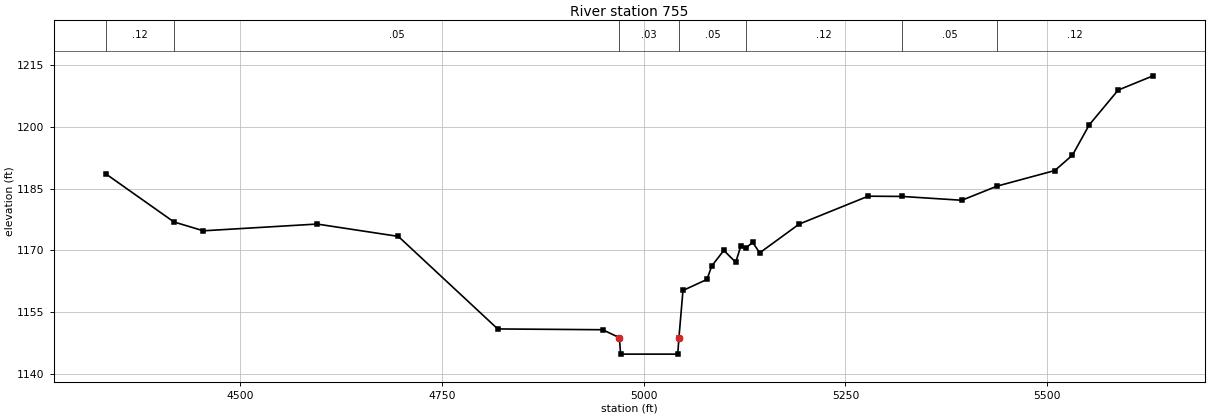
Type RM Length L Ch R = 1,755,0,0,0
BEGIN DESCRIPTION:
CRABAPPLE CREEK 1.0
END DESCRIPTION:
XS GIS Cut Line= 3
      2802555.70     10168053.11      2802929.41     10168009.61
      2803455.69     10167253.10
#Sta/Elev= 30
  4333.5 1188.60  4417.8 1176.93  4454.3 1174.78  4595.2 1176.42  4695.9 1173.42
  4819.1 1150.93  4949.1 1150.74  4969.9 1148.81  4971.4 1144.81  5042.2 1144.81
  5043.7 1148.81  5048.7 1160.28  5078.4 1162.96  5084.4 1166.24  5099.3 1170.01
  5114.1 1167.13  5120.2 1170.97  5126.5 1170.58  5135.1 1171.97  5143.8 1169.42
  5192.7 1176.41  5278.2 1183.19  5320.1 1183.13  5394.3 1182.20  5438.2 1185.65
  5509.5 1189.42  5531.4 1193.16  5552.3 1200.55  5588.1 1208.98  5631.3 1212.44
#Mann=7,-1,0
  4333.5    0.12       0  4417.8    0.05       0  4969.9    0.03       0
  5043.7    0.05       0  5126.5    0.12       0  5320.1    0.05       0
  5438.2    0.12       0
Bank Sta=4969.9,5043.7
Exp/Cntr=0.3,0.1

Chan Stop Cuts=-1