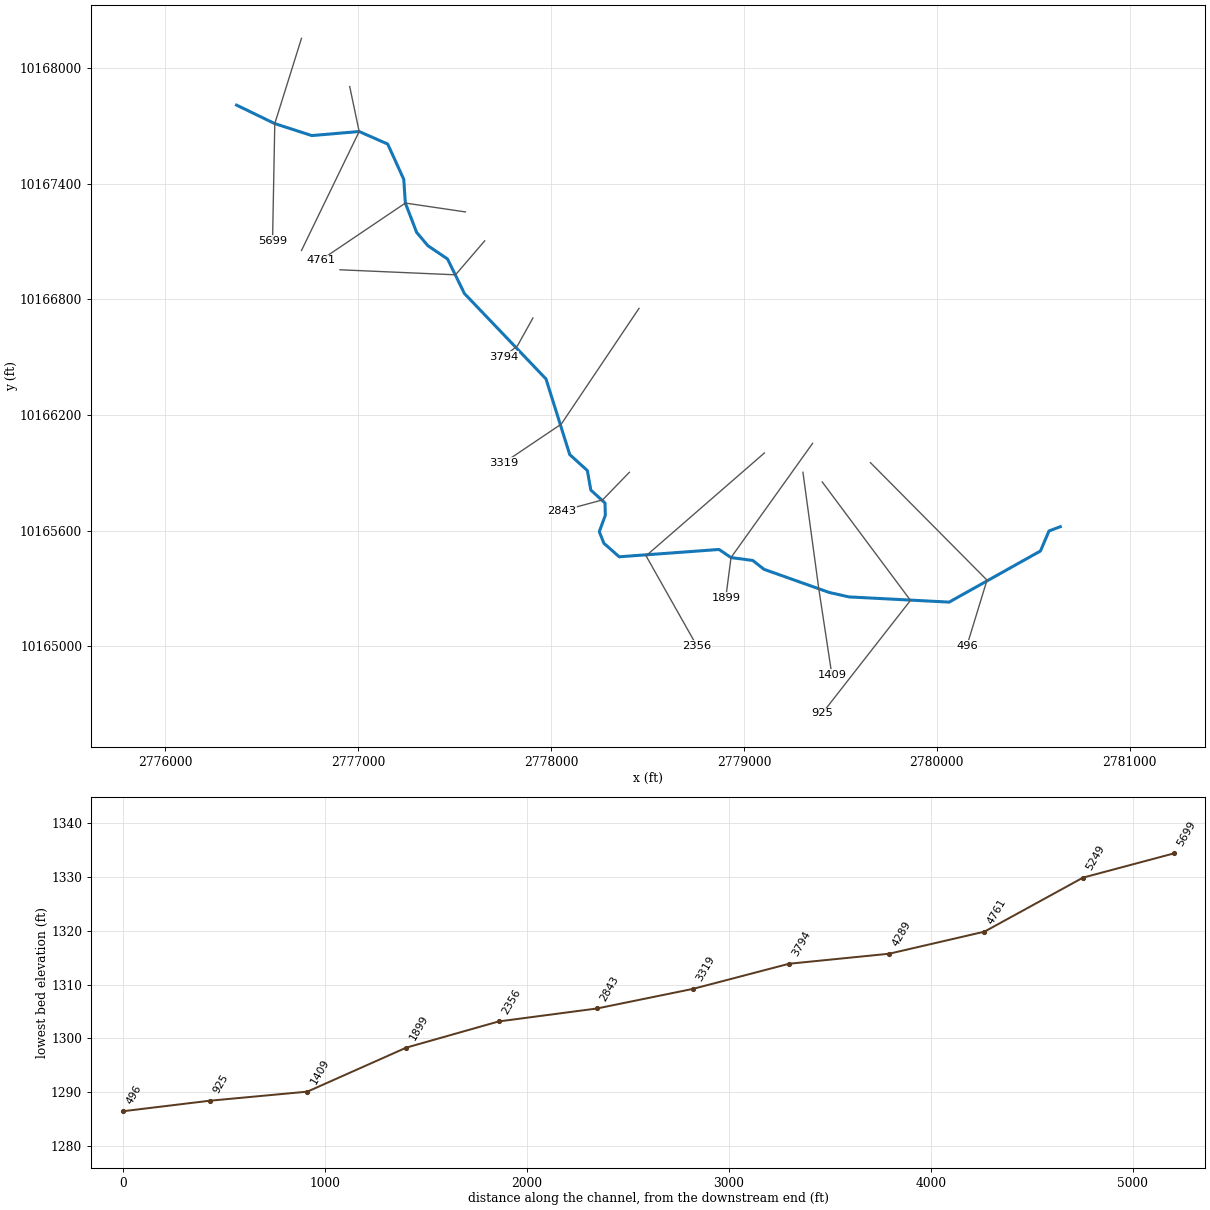
--- HELMS CREEK.prj (project) ---

Proj Title=HELMS CREEK Base Level Engineering
Current Plan=p01
Default Exp/Contr=0.3,0.1
English Units
Geom File=g01
Flow File=f01
Plan File=p01
BEGIN DESCRIPTION:
HELMS CREEK
END DESCRIPTION:

--- HELMS CREEK.p01 (plan) ---

Plan Title=Multiple Run
Short Identifier=Multiple
Geom File=g01
Flow File=f01
Subcritical Flow
K Sum by GR= 0
Std Step Tol= 0.01
Critical Tol= 0.01
Num of Std Step Trials= 20
Max Error Tol= 0.3
Flow Tol Ratio= 0.001
Split Flow NTrial= 30
Split Flow Tol= 0.02
Split Flow Ratio= 0.02
Log Output Level= 0
Friction Slope Method= 1
Unsteady Friction Slope Method= 2
Unsteady Bridges Friction Slope Method= 1
Parabolic Critical Depth
Global Vel Dist=  1 , 1 , 1
Global Log Level= 0
CheckData=True
Encroach Param= -1, 0, 0, 0
BEGIN DESCRIPTION:
Multiple Run
END DESCRIPTION:

--- HELMS CREEK.f01 (steady flow) ---

Flow Title=Multiple
Number of Profiles=7
Profile Names=10-year,25-year,50-year,1pct_min,100-year,1pct_plu,500-year
River Rch & RM= HELMS CREEK,Reach-1,5699
     232     510     850     465    1404    4240    4074
River Rch & RM= HELMS CREEK,Reach-1,2356
     260     577     966     530    1602    4838    4681
Boundary for River Rch & Prof#=HELMS CREEK,Reach-1,1
Up Type=0
Dn Type=3
Dn Slope=0.005
Boundary for River Rch & Prof#=HELMS CREEK,Reach-1,2
Up Type=0
Dn Type=3
Dn Slope=0.005
Boundary for River Rch & Prof#=HELMS CREEK,Reach-1,3
Up Type=0
Dn Type=3
Dn Slope=0.005
Boundary for River Rch & Prof#=HELMS CREEK,Reach-1,4
Up Type=0
Dn Type=3
Dn Slope=0.005
Boundary for River Rch & Prof#=HELMS CREEK,Reach-1,5
Up Type=0
Dn Type=3
Dn Slope=0.005
Boundary for River Rch & Prof#=HELMS CREEK,Reach-1,6
Up Type=0
Dn Type=3
Dn Slope=0.005
Boundary for River Rch & Prof#=HELMS CREEK,Reach-1,7
Up Type=0
Dn Type=3
Dn Slope=0.005

--- HELMS CREEK.g01 (geometry) ---

Geom Title=Existing Conditions

River Reach=HELMS CREEK,Reach-1
Reach XY= 30
      2776369.00     10167807.00      2776567.25     10167711.00
      2776759.00     10167649.00      2777004.75     10167670.00
      2777152.75     10167605.00      2777236.00     10167422.00
      2777244.25     10167299.00      2777302.75     10167147.00
      2777361.00     10167078.00      2777463.00     10167009.00
      2777550.50     10166830.00      2777973.50     10166387.00
      2778096.50     10165995.00      2778188.00     10165912.00
      2778205.75     10165811.00      2778279.50     10165744.00
      2778281.00     10165680.00      2778249.75     10165595.00
      2778273.75     10165535.00      2778353.00     10165465.00
      2778870.50     10165503.00      2778932.75     10165461.00
      2779045.25     10165446.00      2779104.00     10165400.00
      2779442.25     10165280.00      2779544.25     10165257.00
      2780063.75     10165230.00      2780537.25     10165495.00
      2780581.50     10165599.00      2780640.00     10165621.00

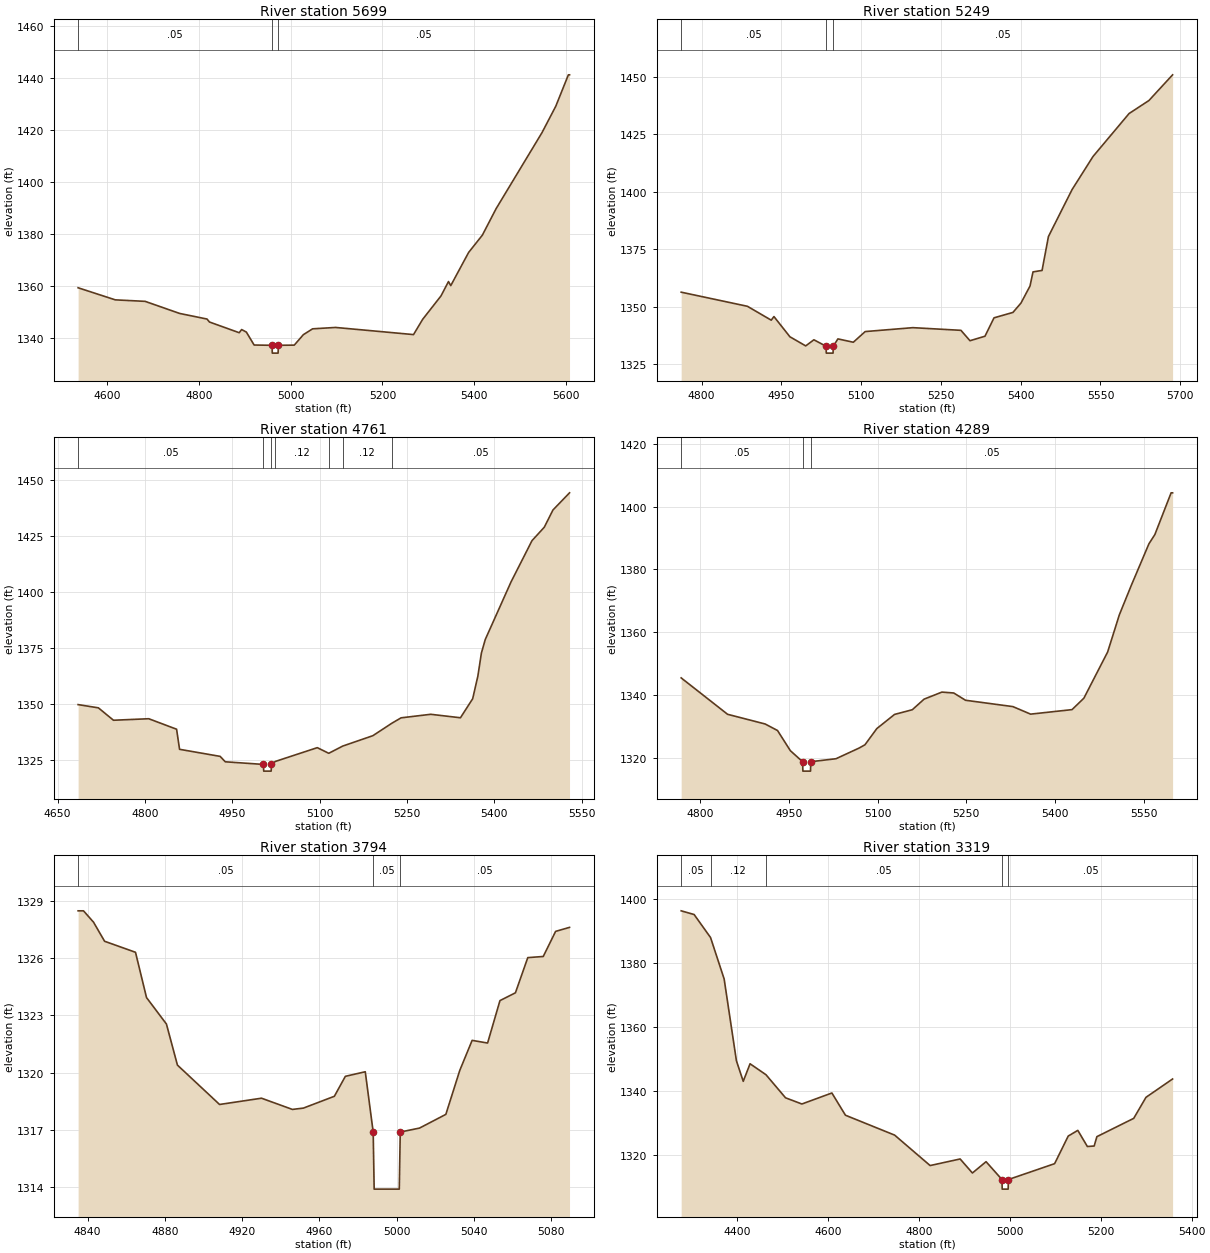
Type RM Length L Ch R = 1,5699,450,450,450
BEGIN DESCRIPTION:
HELMS CREEK 12.0
END DESCRIPTION:
XS GIS Cut Line= 3
      2776705.69     10168153.13      2776567.25     10167711.00
      2776555.68     10167103.11
#Sta/Elev= 30
  4536.7 1359.44  4617.8 1354.80  4682.8 1354.23  4758.1 1349.59  4817.8 1347.44
  4823.0 1346.31  4887.9 1342.20  4893.2 1343.41  4903.5 1342.44  4920.4 1337.48
  4959.5 1337.37  4960.0 1334.37  4972.7 1334.37  4973.2 1337.37  5007.9 1337.44
  5027.9 1341.47  5047.9 1343.69  5097.9 1344.22  5267.9 1341.48  5287.9 1347.35
  5327.9 1356.34  5344.1 1361.82  5349.1 1360.27  5388.0 1372.98  5418.0 1379.63
  5448.0 1389.80  5548.0 1418.95  5578.0 1429.06  5605.5 1441.12  5608.0 1441.12
#Mann=3,-1,0
  4536.7    0.05       0  4959.5    0.03       0  4973.2    0.05       0
Bank Sta=4959.5,4973.2
Exp/Cntr=0.3,0.1

Type RM Length L Ch R = 1,5249,488,488,488
BEGIN DESCRIPTION:
HELMS CREEK 11.0
END DESCRIPTION:
XS GIS Cut Line= 3
      2776955.69     10167903.09      2777004.75     10167670.00
      2776705.67     10167053.08
#Sta/Elev= 30
  4761.8 1356.34  4886.3 1350.21  4931.1 1344.18  4936.2 1345.75  4966.2 1336.97
  4995.9 1333.01  5011.3 1335.66  5034.1 1332.87  5034.6 1329.87  5047.3 1329.87
  5047.8 1332.87  5056.4 1336.05  5085.4 1334.60  5107.7 1339.23  5197.4 1340.93
  5287.7 1339.77  5304.7 1335.26  5332.9 1337.21  5349.9 1345.20  5385.5 1347.55
  5400.6 1351.62  5417.6 1359.03  5423.2 1365.15  5440.2 1365.78  5452.2 1380.51
  5496.6 1400.88  5536.0 1415.26  5603.8 1433.92  5641.1 1439.57  5685.6 1450.73
#Mann=3,-1,0
  4761.8    0.05       0  5034.1    0.03       0  5047.8    0.05       0
Bank Sta=5034.1,5047.8
Exp/Cntr=0.3,0.1

Type RM Length L Ch R = 1,4761,472,472,472
BEGIN DESCRIPTION:
HELMS CREEK 10.0
END DESCRIPTION:
XS GIS Cut Line= 3
      2777555.69     10167253.11      2777244.25     10167299.00
      2776805.72     10167003.14
#Sta/Elev= 30
  4685.2 1349.56  4720.0 1348.12  4745.9 1342.57  4806.5 1343.25  4854.3 1338.56
  4859.4 1329.58  4929.1 1326.42  4937.9 1324.00  5003.4 1322.83  5003.9 1319.83
  5016.7 1319.83  5017.2 1322.83  5023.9 1324.16  5095.9 1330.32  5115.6 1327.80
  5139.6 1331.03  5191.3 1335.67  5224.0 1341.25  5239.8 1343.65  5290.7 1345.23
  5341.7 1343.68  5362.7 1352.18  5371.6 1362.29  5377.7 1372.62  5384.3 1378.65
  5428.6 1404.42  5464.6 1422.86  5485.6 1428.83  5500.6 1436.56  5529.0 1444.22
#Mann=7,-1,0
  4685.2    0.05       0  5003.4    0.03       0  5017.2    0.05       0
  5023.9    0.12       0  5115.6    0.05       0  5139.6    0.12       0
  5224.0    0.05       0
Bank Sta=5003.4,5017.2
Exp/Cntr=0.3,0.1

Type RM Length L Ch R = 1,4289,495,495,495
BEGIN DESCRIPTION:
HELMS CREEK 9.0
END DESCRIPTION:
XS GIS Cut Line= 3
      2777655.71     10167103.14      2777504.25     10166927.00
      2776905.72     10166953.11
#Sta/Elev= 30
  4767.7 1345.44  4846.2 1333.84  4909.8 1330.75  4930.7 1328.67  4952.4 1322.25
  4973.1 1318.73  4973.6 1315.73  4986.5 1315.73  4987.0 1318.73  5029.6 1319.68
  5068.6 1323.07  5078.6 1324.12  5098.7 1329.29  5128.7 1333.80  5158.7 1335.29
  5178.7 1338.67  5208.8 1340.91  5228.8 1340.63  5248.8 1338.31  5328.9 1336.29
  5358.9 1333.89  5429.0 1335.33  5449.0 1338.97  5489.2 1353.69  5509.0 1365.53
  5529.1 1374.86  5559.1 1388.18  5569.1 1391.11  5596.6 1404.41  5599.1 1404.41
#Mann=3,-1,0
  4767.7    0.05       0  4973.1    0.03       0  4987.0    0.05       0
Bank Sta=4973.1,4987
Exp/Cntr=0.3,0.1

Type RM Length L Ch R = 1,3794,475,475,475
BEGIN DESCRIPTION:
HELMS CREEK 8.0
END DESCRIPTION:
XS GIS Cut Line= 3
      2777905.68     10166703.10      2777825.50     10166559.00
      2777755.71     10166503.13
#Sta/Elev= 30
  4835.1 1328.50  4837.9 1328.50  4843.1 1327.90  4848.8 1326.90  4864.8 1326.32
  4870.5 1323.94  4880.8 1322.55  4886.5 1320.39  4908.3 1318.32  4930.0 1318.65
  4946.0 1318.06  4951.7 1318.13  4967.7 1318.75  4973.4 1319.80  4983.7 1320.04
  4987.8 1316.87  4988.3 1313.87  5001.3 1313.87  5001.8 1316.87  5011.8 1317.08
  5025.4 1317.80  5032.6 1320.11  5039.0 1321.69  5047.0 1321.55  5053.4 1323.78
  5061.4 1324.19  5067.8 1326.04  5075.8 1326.10  5082.2 1327.42  5089.4 1327.63
#Mann=3,-1,0
  4835.1    0.05       0  4987.8    0.05       0  5001.8    0.05       0
Bank Sta=4987.8,5001.8
Exp/Cntr=0.3,0.1

Type RM Length L Ch R = 1,3319,476,476,476
BEGIN DESCRIPTION:
HELMS CREEK 7.0
END DESCRIPTION:
XS GIS Cut Line= 3
      2778455.66     10166753.08      2778052.75     10166153.00
      2777755.65     10165953.09
#Sta/Elev= 30
  4277.2 1396.23  4305.7 1395.07  4341.8 1387.88  4371.7 1374.93  4398.7 1349.35
  4413.7 1342.92  4428.7 1348.41  4463.8 1344.97  4506.7 1337.77  4542.7 1335.83
  4608.7 1339.27  4638.5 1332.32  4746.7 1326.10  4824.8 1316.58  4890.8 1318.64
  4917.8 1314.25  4947.8 1317.79  4982.8 1312.21  4983.3 1309.21  4996.4 1309.21
  4996.9 1312.21  5098.6 1317.17  5128.6 1325.81  5149.6 1327.58  5170.6 1322.54
  5185.6 1322.69  5191.6 1325.62  5272.6 1331.34  5299.6 1337.92  5358.1 1343.65
#Mann=5,-1,0
  4277.2    0.05       0  4341.8    0.12       0  4463.8    0.05       0
  4982.8    0.03       0  4996.9    0.05       0
Bank Sta=4982.8,4996.9
Exp/Cntr=0.3,0.1

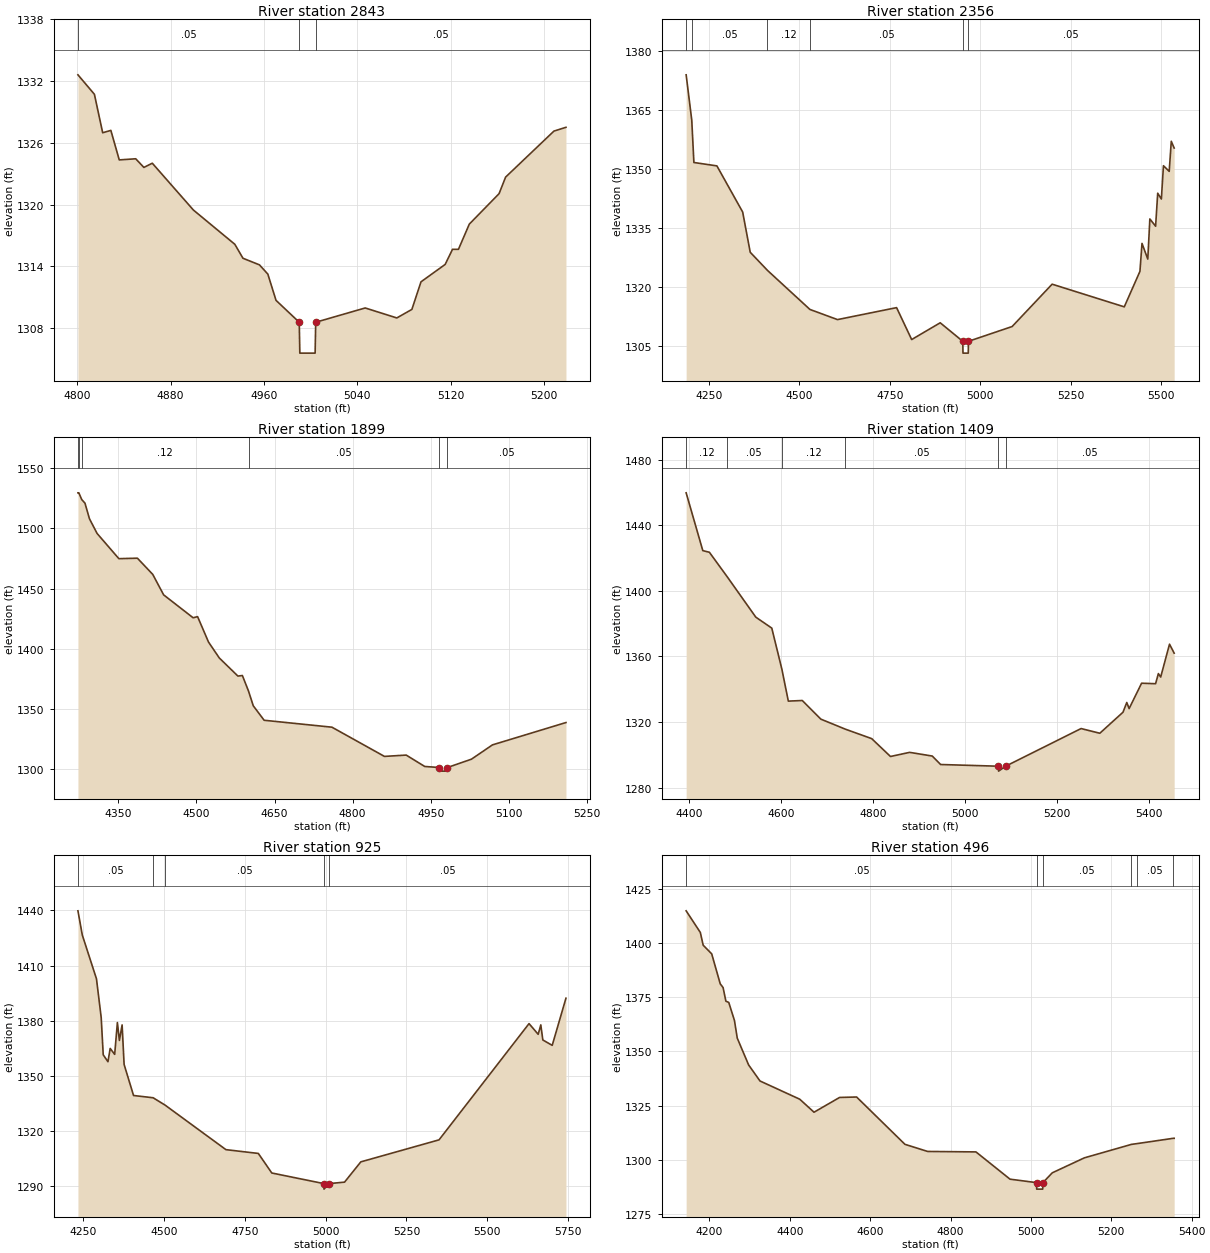
Type RM Length L Ch R = 1,2843,487,487,487
BEGIN DESCRIPTION:
HELMS CREEK 6.0
END DESCRIPTION:
XS GIS Cut Line= 3
      2778405.70     10165903.12      2778267.00     10165760.00
      2778055.72     10165703.12
#Sta/Elev= 30
  4800.7 1332.61  4814.8 1330.72  4821.9 1326.98  4828.9 1327.21  4836.1 1324.34
  4850.2 1324.45  4857.2 1323.61  4864.4 1324.02  4899.6 1319.47  4935.1 1316.14
  4942.1 1314.78  4956.2 1314.14  4963.4 1313.24  4970.4 1310.69  4990.3 1308.56
  4990.8 1305.56  5003.9 1305.56  5004.4 1308.56  5046.8 1309.95  5073.9 1308.98
  5086.8 1309.81  5094.6 1312.49  5115.3 1314.18  5121.6 1315.65  5126.7 1315.65
  5136.0 1318.10  5161.5 1321.06  5167.1 1322.67  5208.5 1327.14  5218.8 1327.51
#Mann=3,-1,0
  4800.7    0.05       0  4990.3    0.03       0  5004.4    0.05       0
Bank Sta=4990.3,5004.4
Exp/Cntr=0.3,0.1

Type RM Length L Ch R = 1,2356,457,457,457
BEGIN DESCRIPTION:
HELMS CREEK 5.0
END DESCRIPTION:
XS GIS Cut Line= 3
      2779105.67     10166003.10      2778492.25     10165470.00
      2778755.69     10165003.09
#Sta/Elev= 30
  4187.3 1373.87  4202.8 1362.36  4208.7 1351.59  4272.3 1350.73  4343.5 1339.01
  4364.4 1328.78  4412.1 1324.17  4529.4 1314.25  4605.6 1311.67  4768.9 1314.71
  4810.6 1306.60  4889.5 1310.86  4951.9 1306.15  4952.4 1303.15  4967.0 1303.15
  4967.5 1306.15  5088.3 1309.91  5198.8 1320.67  5398.2 1314.91  5441.5 1323.93
  5447.2 1331.03  5463.2 1327.05  5468.9 1337.25  5484.8 1335.40  5490.6 1343.79
  5500.7 1342.31  5506.5 1350.77  5522.4 1349.34  5528.1 1356.98  5536.1 1355.27
#Mann=6,-1,0
  4187.3    0.12       0  4202.8    0.05       0  4412.1    0.12       0
  4529.4    0.05       0  4951.9    0.05       0  4967.5    0.05       0
Bank Sta=4951.9,4967.5
Exp/Cntr=0.3,0.1

Type RM Length L Ch R = 1,1899,490,490,490
BEGIN DESCRIPTION:
HELMS CREEK 4.0
END DESCRIPTION:
XS GIS Cut Line= 3
      2779355.66     10166053.07      2778932.75     10165461.00
      2778905.69     10165253.15
#Sta/Elev= 30
  4272.4 1529.62  4274.1 1529.62  4279.7 1524.02  4285.9 1521.02  4294.5 1508.08
  4309.2 1495.84  4351.0 1474.89  4386.6 1475.29  4416.1 1461.81  4437.0 1444.80
  4493.6 1425.77  4502.2 1426.70  4523.1 1405.63  4543.9 1392.33  4579.6 1377.30
  4588.2 1377.76  4600.0 1364.82  4609.1 1352.60  4630.0 1340.56  4760.2 1334.81
  4861.0 1310.53  4902.8 1311.62  4938.4 1302.16  4966.2 1301.29  4966.7 1298.29
  4981.4 1298.29  4981.9 1301.29  5028.1 1308.22  5068.5 1320.12  5209.6 1338.67
#Mann=6,-1,0
  4272.4    0.12       0  4274.1    0.05       0  4279.7    0.12       0
  4600.0    0.05       0  4966.2    0.05       0  4981.9    0.05       0
Bank Sta=4966.2,4981.9
Exp/Cntr=0.3,0.1

Type RM Length L Ch R = 1,1409,484,484,484
BEGIN DESCRIPTION:
HELMS CREEK 3.0
END DESCRIPTION:
XS GIS Cut Line= 3
      2779305.68     10165903.16      2779387.50     10165302.00
      2779455.68     10164853.15
#Sta/Elev= 30
  4393.3 1459.76  4429.5 1424.53  4443.8 1423.52  4481.4 1409.04  4544.7 1383.97
  4579.4 1377.29  4601.3 1352.34  4615.4 1332.78  4645.7 1333.16  4686.0 1321.81
  4739.5 1315.67  4796.6 1309.92  4837.4 1299.03  4879.1 1301.55  4928.2 1299.30
  4946.4 1294.14  5071.9 1293.11  5072.4 1290.11  5087.7 1293.11  5251.7 1316.06
  5292.4 1313.20  5342.8 1326.02  5351.0 1331.95  5356.1 1328.24  5383.2 1343.70
  5413.6 1343.40  5419.7 1349.57  5424.7 1347.47  5443.9 1367.50  5454.0 1362.02
#Mann=6,-1,0
  4393.3    0.12       0  4481.4    0.05       0  4601.3    0.12       0
  4739.5    0.05       0  5071.9    0.03       0  5087.7    0.05       0
Bank Sta=5071.9,5087.7
Exp/Cntr=0.3,0.1

Type RM Length L Ch R = 1,925,429,429,429
BEGIN DESCRIPTION:
HELMS CREEK 2.0
END DESCRIPTION:
XS GIS Cut Line= 3
      2779405.70     10165853.09      2779863.25     10165239.00
      2779405.68     10164653.11
#Sta/Elev= 30
  4234.2 1439.73  4247.7 1426.56  4291.5 1402.77  4306.1 1381.77  4312.4 1361.45
  4327.0 1357.68  4333.9 1364.91  4347.8 1361.69  4356.2 1378.98  4362.4 1369.26
  4370.8 1377.70  4377.0 1356.18  4406.2 1339.32  4466.6 1338.10  4503.6 1334.11
  4691.9 1309.88  4792.0 1307.83  4833.7 1297.19  4994.7 1291.42  4995.2 1288.42
  5010.5 1291.42  5058.7 1292.22  5109.0 1303.24  5350.9 1315.21  5629.2 1378.41
  5657.5 1372.60  5665.6 1377.71  5671.9 1369.51  5700.9 1366.59  5743.4 1392.23
#Mann=5,-1,0
  4234.2    0.05       0  4466.6    0.12       0  4503.6    0.05       0
  4994.7    0.03       0  5010.5    0.05       0
Bank Sta=4994.7,5010.5
Exp/Cntr=0.3,0.1

Type RM Length L Ch R = 1,496,0,0,0
BEGIN DESCRIPTION:
HELMS CREEK 1.0
END DESCRIPTION:
XS GIS Cut Line= 3
      2779655.70     10165953.09      2780260.00     10165344.00
      2780155.68     10165003.10
#Sta/Elev= 30
  4142.0 1414.86  4177.3 1404.88  4184.4 1399.00  4205.6 1395.01  4226.8 1381.20
  4233.9 1379.47  4240.9 1373.16  4248.0 1372.62  4262.2 1364.29  4269.2 1356.13
  4297.5 1343.75  4325.8 1336.36  4424.8 1327.94  4460.2 1321.95  4523.8 1328.76
  4566.2 1328.97  4686.5 1307.14  4743.0 1303.85  4863.2 1303.64  4948.1 1291.06
  5013.9 1289.47  5014.4 1286.47  5029.3 1286.47  5029.8 1289.47  5053.2 1294.00
  5133.0 1300.90  5250.3 1307.12  5264.2 1307.47  5354.4 1309.92  5356.5 1309.92
#Mann=6,-1,0
  4142.0    0.05       0  5013.9    0.05       0  5029.8    0.05       0
  5250.3    0.12       0  5264.2    0.05       0  5354.4    0.12       0
Bank Sta=5013.9,5029.8
Exp/Cntr=0.3,0.1

Chan Stop Cuts=-1