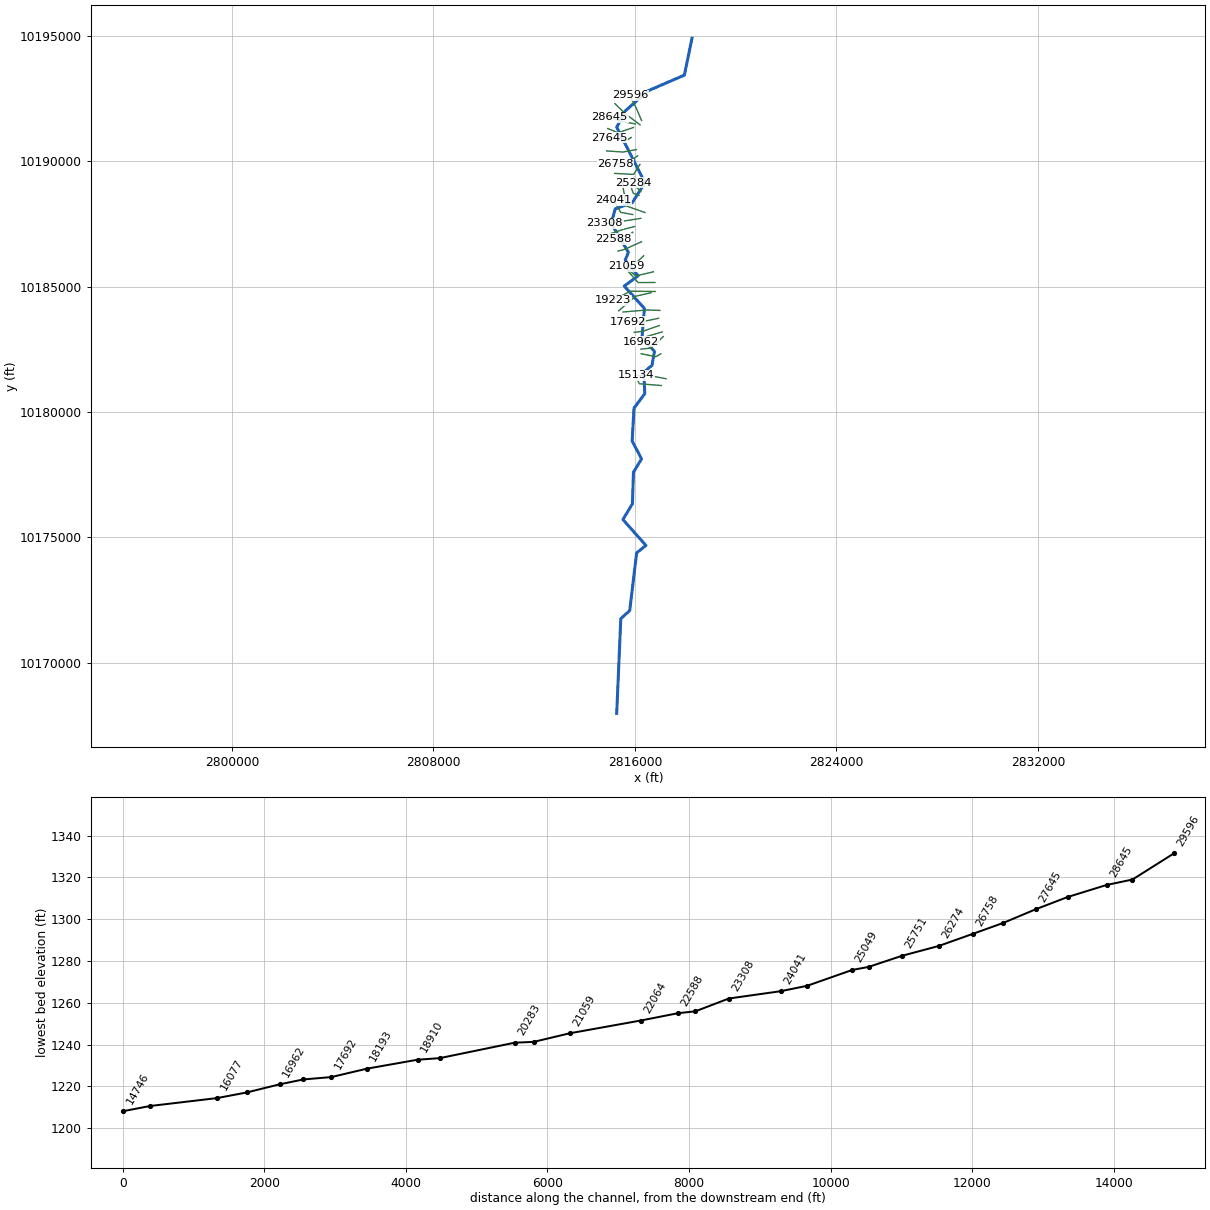
--- HONDO CREEK.prj (project) ---

Proj Title=HONDO CREEK Base Level Engineering
Current Plan=p01
Default Exp/Contr=0.3,0.1
English Units
Geom File=g01
Flow File=f01
Plan File=p01
BEGIN DESCRIPTION:
HONDO CREEK
END DESCRIPTION:

--- HONDO CREEK.p01 (plan) ---

Plan Title=Multiple Run
Short Identifier=Multiple
Geom File=g01
Flow File=f01
Subcritical Flow
K Sum by GR= 0
Std Step Tol= 0.01
Critical Tol= 0.01
Num of Std Step Trials= 20
Max Error Tol= 0.3
Flow Tol Ratio= 0.001
Split Flow NTrial= 30
Split Flow Tol= 0.02
Split Flow Ratio= 0.02
Log Output Level= 0
Friction Slope Method= 1
Unsteady Friction Slope Method= 2
Unsteady Bridges Friction Slope Method= 1
Parabolic Critical Depth
Global Vel Dist=  1 , 1 , 1
Global Log Level= 0
CheckData=True
Encroach Param= -1, 0, 0, 0
BEGIN DESCRIPTION:
Multiple Run
END DESCRIPTION:

--- HONDO CREEK.f01 (steady flow) ---

Flow Title=Multiple
Number of Profiles=7
Profile Names=10-year,25-year,50-year,1pct_min,100-year,1pct_plu,500-year
River Rch & RM= HONDO CREEK,Reach-1,29596
     119     243     392     209     631    1905    1743
River Rch & RM= HONDO CREEK,Reach-1,23308
     148     311     508     273     826    2493    2322
River Rch & RM= HONDO CREEK,Reach-1,19223
     202     442     733     400    1207    3644    3473
River Rch & RM= HONDO CREEK,Reach-1,15134
     303     682    1151     635    1918    5794    5660
River Rch & RM= HONDO CREEK,Reach-1,4380
     306     690    1165     643    1943    5868    5737
Boundary for River Rch & Prof#=HONDO CREEK,Reach-1,1
Up Type=0
Dn Type=3
Dn Slope=0.005
Boundary for River Rch & Prof#=HONDO CREEK,Reach-1,2
Up Type=0
Dn Type=3
Dn Slope=0.005
Boundary for River Rch & Prof#=HONDO CREEK,Reach-1,3
Up Type=0
Dn Type=3
Dn Slope=0.005
Boundary for River Rch & Prof#=HONDO CREEK,Reach-1,4
Up Type=0
Dn Type=3
Dn Slope=0.005
Boundary for River Rch & Prof#=HONDO CREEK,Reach-1,5
Up Type=0
Dn Type=3
Dn Slope=0.005
Boundary for River Rch & Prof#=HONDO CREEK,Reach-1,6
Up Type=0
Dn Type=3
Dn Slope=0.005
Boundary for River Rch & Prof#=HONDO CREEK,Reach-1,7
Up Type=0
Dn Type=3
Dn Slope=0.005

--- HONDO CREEK.g01 (geometry) ---

Geom Title=Existing Conditions

River Reach=HONDO CREEK,Reach-1
Reach XY= 30
      2818267.50     10194905.00      2817963.75     10193434.00
      2816521.00     10192812.00      2815627.00     10192017.00
      2815279.00     10191360.00      2816397.75     10189145.00
      2815896.00     10188349.00      2815218.75     10188099.00
      2815063.00     10187516.00      2815742.25     10186367.00
      2815617.50     10186057.00      2816130.00     10185431.00
      2815577.00     10185020.00      2816380.25     10184125.00
      2816281.25     10182969.00      2816776.75     10182411.00
      2816679.75     10181860.00      2816351.75     10181575.00
      2816394.25     10180730.00      2815964.75     10180148.00
      2815891.50     10178837.00      2816265.25     10178123.00
      2815944.00     10177592.00      2815902.00     10176332.00
      2815524.75     10175704.00      2816439.25     10174671.00
      2816069.50     10174374.00      2815795.00     10172073.00
      2815441.00     10171747.00      2815278.00     10167970.00

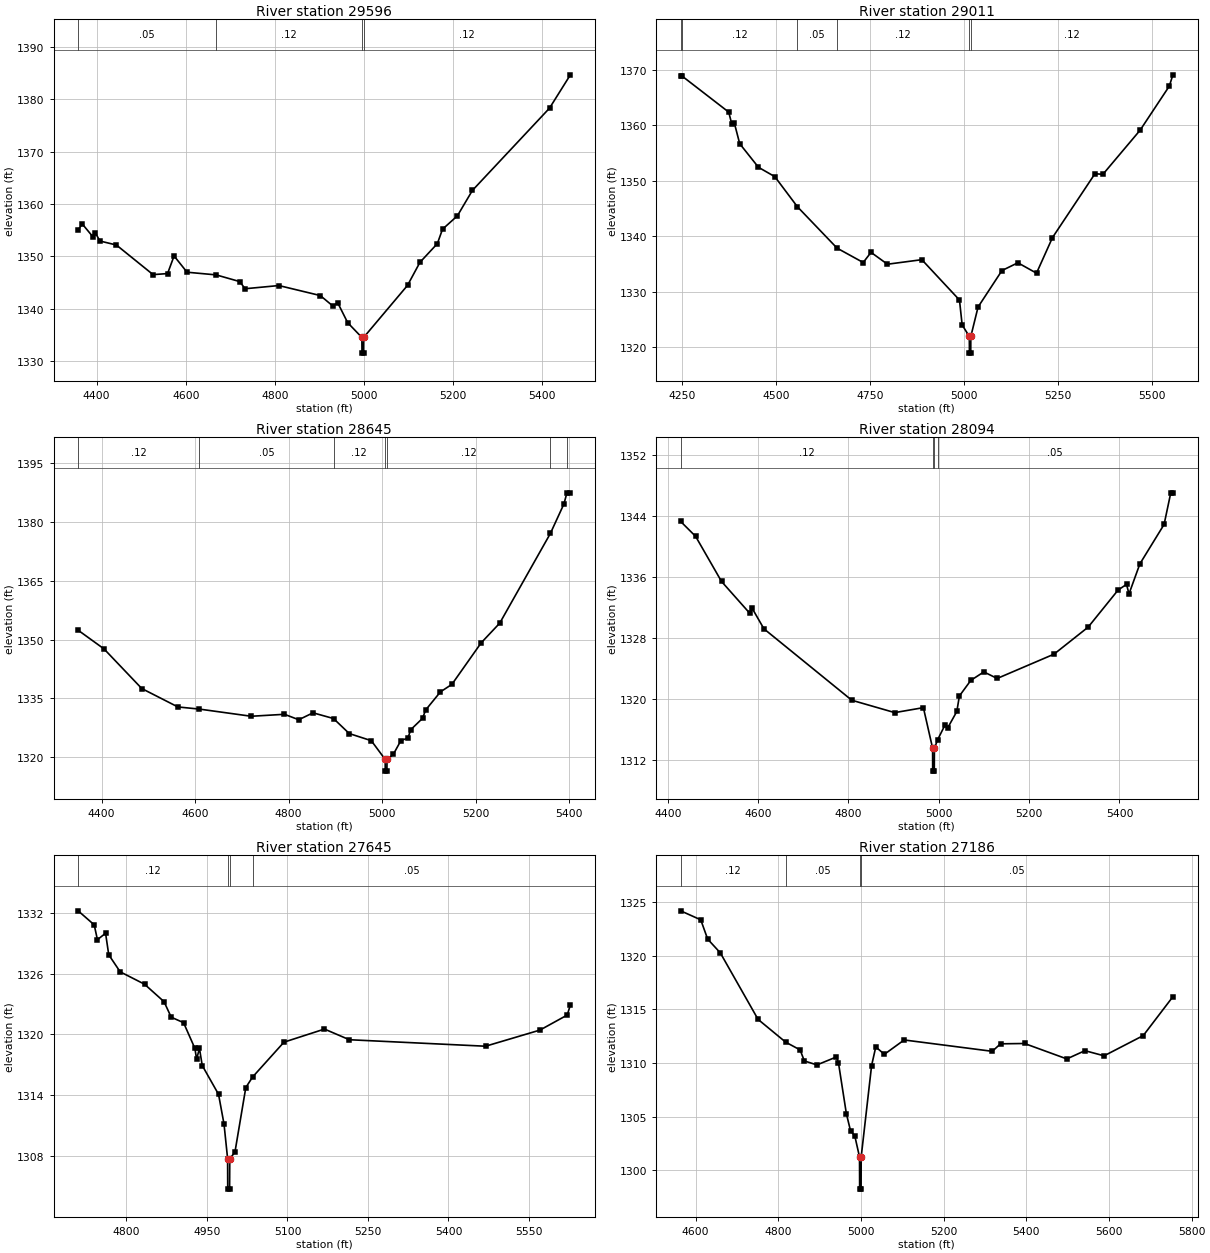
Type RM Length L Ch R = 1,29596,585,585,585
BEGIN DESCRIPTION:
HONDO CREEK 59.0
END DESCRIPTION:
XS GIS Cut Line= 3
      2816263.69     10191628.28      2816065.01     10192098.93
      2815799.62     10192629.71
#Sta/Elev= 30
  4358.7 1355.05  4367.9 1356.18  4391.6 1353.74  4397.0 1354.52  4407.4 1352.92
  4444.5 1352.15  4526.8 1346.49  4559.3 1346.69  4573.9 1350.06  4603.0 1346.95
  4668.3 1346.44  4721.6 1345.15  4733.0 1343.79  4809.0 1344.40  4901.9 1342.49
  4930.1 1340.49  4941.0 1341.11  4963.4 1337.30  4995.2 1334.48  4995.5 1331.48
  4999.0 1331.48  4999.2 1334.48  5097.6 1344.43  5125.5 1348.84  5164.6 1352.42
  5176.1 1355.17  5209.4 1357.72  5243.2 1362.59  5416.2 1378.32  5463.0 1384.69
#Mann=4,-1,0
  4358.7    0.05       0  4668.3    0.12       0  4995.2    0.07       0
  4999.2    0.12       0
Bank Sta=4995.2,4999.2
Exp/Cntr=0.3,0.1

Type RM Length L Ch R = 1,29011,366,366,366
BEGIN DESCRIPTION:
HONDO CREEK 58.0
END DESCRIPTION:
XS GIS Cut Line= 3
      2816205.70     10191453.10      2815629.10     10191888.69
      2815208.62     10192299.52
#Sta/Elev= 30
  4245.3 1368.97  4247.8 1368.97  4373.3 1362.41  4381.6 1360.19  4387.9 1360.53
  4402.5 1356.72  4452.4 1352.47  4496.0 1350.78  4556.2 1345.35  4661.7 1337.90
  4731.3 1335.31  4752.1 1337.14  4795.8 1335.00  4887.4 1335.82  4987.6 1328.55
  4994.7 1324.07  5013.8 1321.98  5014.1 1318.98  5017.6 1318.98  5017.8 1321.98
  5037.1 1327.29  5100.7 1333.86  5143.1 1335.26  5192.7 1333.39  5235.2 1339.80
  5348.3 1351.31  5369.5 1351.20  5468.5 1359.15  5546.2 1367.09  5555.8 1369.13
#Mann=6,-1,0
  4245.3    0.05       0  4247.8    0.12       0  4556.2    0.05       0
  4661.7    0.12       0  5013.8    0.07       0  5017.8    0.12       0
Bank Sta=5013.8,5017.8
Exp/Cntr=0.3,0.1

Type RM Length L Ch R = 1,28645,551,551,551
BEGIN DESCRIPTION:
HONDO CREEK 57.0
END DESCRIPTION:
XS GIS Cut Line= 3
      2816019.49     10191488.80      2815468.74     10191591.66
      2815002.64     10191750.50
#Sta/Elev= 30
  4349.9 1352.37  4405.2 1347.60  4486.0 1337.47  4563.2 1332.77  4609.2 1332.22
  4720.0 1330.39  4791.2 1330.89  4821.7 1329.50  4852.2 1331.27  4896.0 1329.81
  4929.7 1325.97  4976.8 1324.15  5006.5 1319.37  5006.7 1316.37  5010.2 1316.37
  5010.5 1319.37  5023.8 1320.63  5040.2 1324.19  5055.1 1324.82  5061.3 1326.97
  5086.5 1329.87  5093.0 1331.98  5124.7 1336.62  5149.2 1338.54  5211.8 1349.15
  5251.5 1354.18  5359.8 1377.10  5388.8 1384.64  5395.0 1387.38  5402.6 1387.48
#Mann=7,-1,0
  4349.9    0.12       0  4609.2    0.05       0  4896.0    0.12       0
  5006.5    0.07       0  5010.5    0.12       0  5359.8    0.05       0
  5395.0    0.12       0
Bank Sta=5006.5,5010.5
Exp/Cntr=0.3,0.1

Type RM Length L Ch R = 1,28094,449,449,449
BEGIN DESCRIPTION:
HONDO CREEK 56.0
END DESCRIPTION:
XS GIS Cut Line= 3
      2815944.01     10191348.17      2815332.02     10191138.53
      2814921.89     10191305.19
#Sta/Elev= 30
  4428.7 1343.28  4461.8 1341.33  4519.1 1335.43  4581.7 1331.26  4587.0 1331.91
  4613.0 1329.23  4807.5 1319.88  4902.6 1318.26  4966.0 1318.91  4986.4 1313.60
  4986.6 1310.60  4990.1 1310.60  4990.4 1313.60  4997.6 1314.72  5014.4 1316.70
  5019.7 1316.25  5040.0 1318.41  5045.7 1320.44  5071.0 1322.48  5099.8 1323.59
  5129.3 1322.73  5255.1 1325.91  5330.7 1329.45  5397.1 1334.31  5415.7 1335.05
  5421.1 1333.79  5445.2 1337.73  5498.8 1342.89  5513.6 1347.03  5518.3 1347.03
#Mann=4,-1,0
  4428.7    0.12       0  4986.4    0.05       0  4990.4    0.12       0
  4997.6    0.05       0
Bank Sta=4986.4,4990.4
Exp/Cntr=0.3,0.1

Type RM Length L Ch R = 1,27645,459,459,459
BEGIN DESCRIPTION:
HONDO CREEK 55.0
END DESCRIPTION:
XS GIS Cut Line= 3
      2815851.53     10190947.11      2815665.35     10190827.33
      2814979.89     10190947.00
#Sta/Elev= 30
  4710.0 1332.18  4739.9 1330.80  4745.9 1329.34  4761.1 1329.97  4767.0 1327.85
  4788.3 1326.17  4833.7 1324.95  4870.0 1323.23  4883.4 1321.70  4906.4 1321.16
  4927.5 1318.63  4930.7 1317.56  4936.0 1318.63  4941.2 1316.94  4971.6 1314.10
  4981.8 1311.17  4988.5 1307.76  4988.7 1304.76  4992.2 1304.76  4992.5 1307.76
  5002.1 1308.39  5022.4 1314.77  5035.1 1315.81  5093.5 1319.24  5169.0 1320.53
  5215.3 1319.48  5469.1 1318.84  5570.5 1320.43  5621.3 1321.91  5627.2 1322.91
#Mann=4,-1,0
  4710.0    0.12       0  4988.5    0.07       0  4992.5    0.12       0
  5035.1    0.05       0
Bank Sta=4988.5,4992.5
Exp/Cntr=0.3,0.1

Type RM Length L Ch R = 1,27186,428,428,428
BEGIN DESCRIPTION:
HONDO CREEK 54.0
END DESCRIPTION:
XS GIS Cut Line= 3
      2816059.89     10190466.66      2815523.43     10190367.70
      2814879.74     10190413.21
#Sta/Elev= 30
  4563.8 1324.21  4612.4 1323.37  4629.1 1321.57  4659.6 1320.29  4751.1 1314.07
  4817.7 1311.95  4852.8 1311.22  4863.0 1310.19  4893.5 1309.82  4940.4 1310.56
  4945.5 1310.03  4964.7 1305.26  4974.8 1303.66  4985.0 1303.20  4996.5 1301.22
  4996.8 1298.22  5000.3 1298.22  5000.5 1301.22  5025.7 1309.76  5035.8 1311.50
  5056.6 1310.81  5104.5 1312.15  5317.6 1311.09  5337.6 1311.79  5395.7 1311.82
  5498.0 1310.38  5541.8 1311.15  5588.2 1310.67  5682.9 1312.56  5754.6 1316.19
#Mann=4,-1,0
  4563.8    0.12       0  4817.7    0.05       0  4996.5    0.05       0
  5000.5    0.05       0
Bank Sta=4996.5,5000.5
Exp/Cntr=0.3,0.1

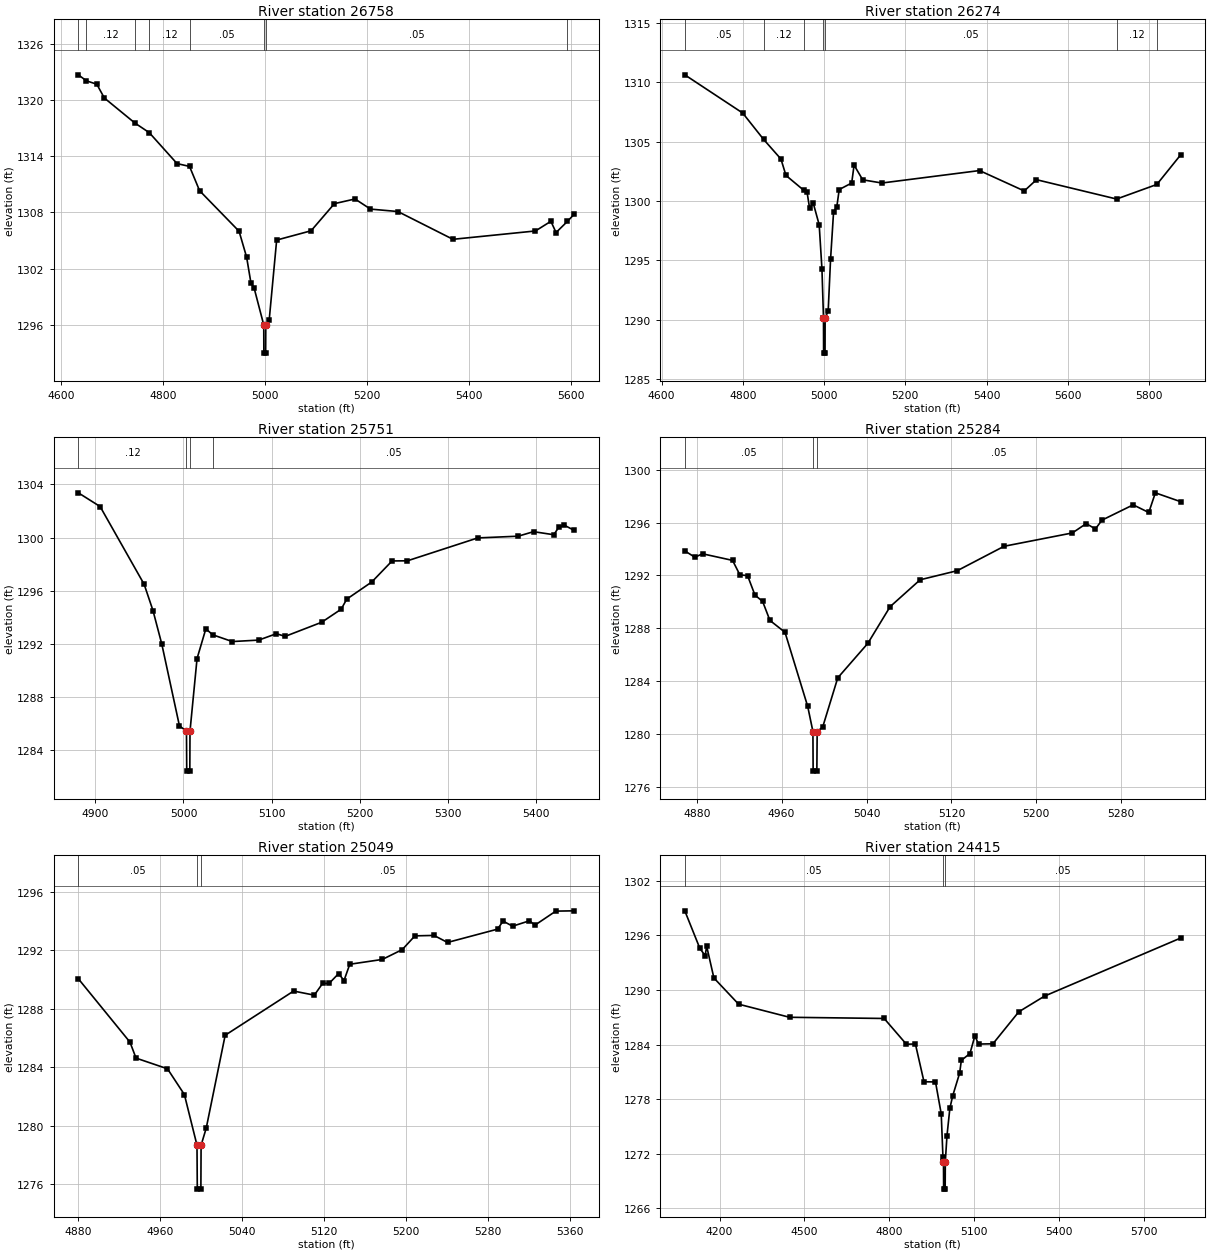
Type RM Length L Ch R = 1,26758,484,484,484
BEGIN DESCRIPTION:
HONDO CREEK 53.0
END DESCRIPTION:
XS GIS Cut Line= 3
      2816111.94     10190217.93      2815740.88     10189952.33
      2815230.56     10189878.13
#Sta/Elev= 30
  4634.2 1322.67  4650.1 1322.03  4670.4 1321.67  4685.2 1320.20  4744.9 1317.54
  4773.2 1316.51  4827.7 1313.21  4852.2 1312.91  4871.9 1310.32  4949.3 1306.00
  4964.1 1303.24  4972.6 1300.48  4978.8 1299.95  4997.7 1296.01  4997.9 1293.01
  5001.4 1293.01  5001.7 1296.01  5008.3 1296.50  5023.0 1305.06  5090.5 1306.05
  5136.2 1308.94  5176.6 1309.44  5206.9 1308.36  5260.7 1308.10  5368.6 1305.14
  5530.3 1306.03  5560.6 1307.06  5570.7 1305.86  5592.8 1307.04  5606.2 1307.81
#Mann=8,-1,0
  4634.2    0.05       0  4650.1    0.12       0  4744.9    0.05       0
  4773.2    0.12       0  4852.2    0.05       0  4997.7    0.05       0
  5001.7    0.05       0  5592.8    0.12       0
Bank Sta=4997.7,5001.7
Exp/Cntr=0.3,0.1

Type RM Length L Ch R = 1,26274,523,523,523
BEGIN DESCRIPTION:
HONDO CREEK 52.0
END DESCRIPTION:
XS GIS Cut Line= 3
      2816199.19     10189874.18      2815951.81     10189475.77
      2815201.34     10189515.70
#Sta/Elev= 30
  4657.1 1310.64  4799.6 1307.42  4851.0 1305.20  4893.8 1303.54  4906.1 1302.16
  4949.9 1300.91  4958.1 1300.73  4964.4 1299.38  4973.4 1299.81  4987.9 1298.00
  4994.7 1294.27  4998.5 1290.18  4998.8 1287.18  5002.3 1287.18  5002.5 1290.18
  5010.0 1290.70  5015.9 1295.09  5023.3 1299.07  5031.3 1299.52  5037.2 1300.97
  5067.9 1301.52  5073.8 1303.03  5095.0 1301.79  5142.2 1301.52  5382.6 1302.57
  5492.7 1300.85  5522.8 1301.80  5720.0 1300.17  5819.1 1301.40  5877.6 1303.89
#Mann=7,-1,0
  4657.1    0.05       0  4851.0    0.12       0  4949.9    0.05       0
  4998.5    0.05       0  5002.5    0.05       0  5720.0    0.12       0
  5819.1    0.05       0
Bank Sta=4998.5,5002.5
Exp/Cntr=0.3,0.1

Type RM Length L Ch R = 1,25751,467,467,467
BEGIN DESCRIPTION:
HONDO CREEK 51.0
END DESCRIPTION:
XS GIS Cut Line= 3
      2816510.42     10189229.24      2816249.99     10189229.24
      2815975.68     10189355.98
#Sta/Elev= 30
  4880.7 1303.36  4905.4 1302.33  4955.4 1296.48  4965.4 1294.51  4975.4 1291.99
  4995.4 1285.85  5003.4 1285.44  5003.7 1282.44  5007.2 1282.44  5007.4 1285.44
  5015.4 1290.90  5025.4 1293.14  5033.1 1292.69  5055.4 1292.18  5085.4 1292.29
  5105.4 1292.77  5115.4 1292.57  5156.8 1293.63  5178.9 1294.61  5185.3 1295.37
  5213.7 1296.66  5236.7 1298.24  5254.1 1298.25  5333.9 1299.97  5379.8 1300.10
  5397.2 1300.44  5420.2 1300.21  5425.7 1300.76  5432.3 1300.92  5443.3 1300.54
#Mann=4,-1,0
  4880.7    0.12       0  5003.4    0.07       0  5007.4    0.12       0
  5033.1    0.05       0
Bank Sta=5003.4,5007.4
Exp/Cntr=0.3,0.1

Type RM Length L Ch R = 1,25284,235,235,235
BEGIN DESCRIPTION:
HONDO CREEK 50.0
END DESCRIPTION:
XS GIS Cut Line= 3
      2816234.35     10188788.28      2816067.01     10188963.01
      2815935.73     10189145.94
#Sta/Elev= 30
  4868.8 1293.86  4878.3 1293.38  4885.5 1293.64  4913.8 1293.14  4920.7 1292.04
  4927.9 1291.99  4934.9 1290.51  4942.1 1290.03  4949.0 1288.59  4963.2 1287.69
  4984.6 1282.07  4989.5 1280.17  4989.7 1277.17  4993.2 1277.17  4993.5 1280.17
  4998.7 1280.51  5012.9 1284.24  5041.2 1286.85  5062.2 1289.63  5090.5 1291.67
  5125.5 1292.36  5169.6 1294.21  5233.9 1295.22  5247.0 1295.93  5255.6 1295.52
  5261.8 1296.19  5291.2 1297.35  5305.9 1296.77  5312.1 1298.26  5335.9 1297.59
#Mann=3,-1,0
  4868.8    0.05       0  4989.5    0.05       0  4993.5    0.05       0
Bank Sta=4989.5,4993.5
Exp/Cntr=0.3,0.1

Type RM Length L Ch R = 1,25049,634,634,634
BEGIN DESCRIPTION:
HONDO CREEK 49.0
END DESCRIPTION:
XS GIS Cut Line= 3
      2816163.17     10188638.97      2815936.81     10188719.99
      2815856.46     10188949.83
#Sta/Elev= 30
  4880.2 1290.04  4930.6 1285.71  4936.5 1284.62  4967.2 1283.89  4983.7 1282.13
  4996.0 1278.67  4996.3 1275.67  4999.8 1275.67  5000.0 1278.67  5005.0 1279.83
  5023.5 1286.18  5090.3 1289.20  5110.5 1288.92  5118.6 1289.72  5124.9 1289.72
  5134.2 1290.39  5139.5 1289.92  5145.1 1291.03  5176.9 1291.36  5196.3 1292.03
  5208.7 1292.97  5227.3 1293.00  5240.5 1292.52  5289.4 1293.43  5294.7 1293.98
  5304.0 1293.63  5320.5 1294.00  5325.8 1293.70  5346.2 1294.66  5364.1 1294.68
#Mann=3,-1,0
  4880.2    0.05       0  4996.0    0.05       0  5000.0    0.05       0
Bank Sta=4996,5000
Exp/Cntr=0.3,0.1

Type RM Length L Ch R = 1,24415,374,374,374
BEGIN DESCRIPTION:
HONDO CREEK 48.0
END DESCRIPTION:
XS GIS Cut Line= 3
      2816405.73     10187953.10      2815662.92     10188215.75
      2815493.05     10189166.72
#Sta/Elev= 30
  4077.0 1298.68  4130.1 1294.57  4149.0 1293.75  4154.3 1294.80  4179.9 1291.31
  4267.3 1288.43  4447.5 1286.99  4782.2 1286.86  4860.8 1284.03  4892.7 1284.06
  4923.1 1279.91  4963.8 1279.89  4984.1 1276.38  4990.2 1271.61  4992.1 1271.12
  4992.6 1268.12  4998.0 1268.12  4998.5 1271.12  5004.4 1273.98  5014.6 1276.99
  5024.7 1278.37  5049.2 1280.86  5055.2 1282.26  5085.7 1283.01  5103.0 1284.94
  5116.2 1284.05  5167.0 1284.08  5258.4 1287.59  5349.8 1289.32  5830.9 1295.69
#Mann=3,-1,0
  4077.0    0.05       0  4992.1    0.05       0  4998.5    0.05       0
Bank Sta=4992.1,4998.5
Exp/Cntr=0.3,0.1

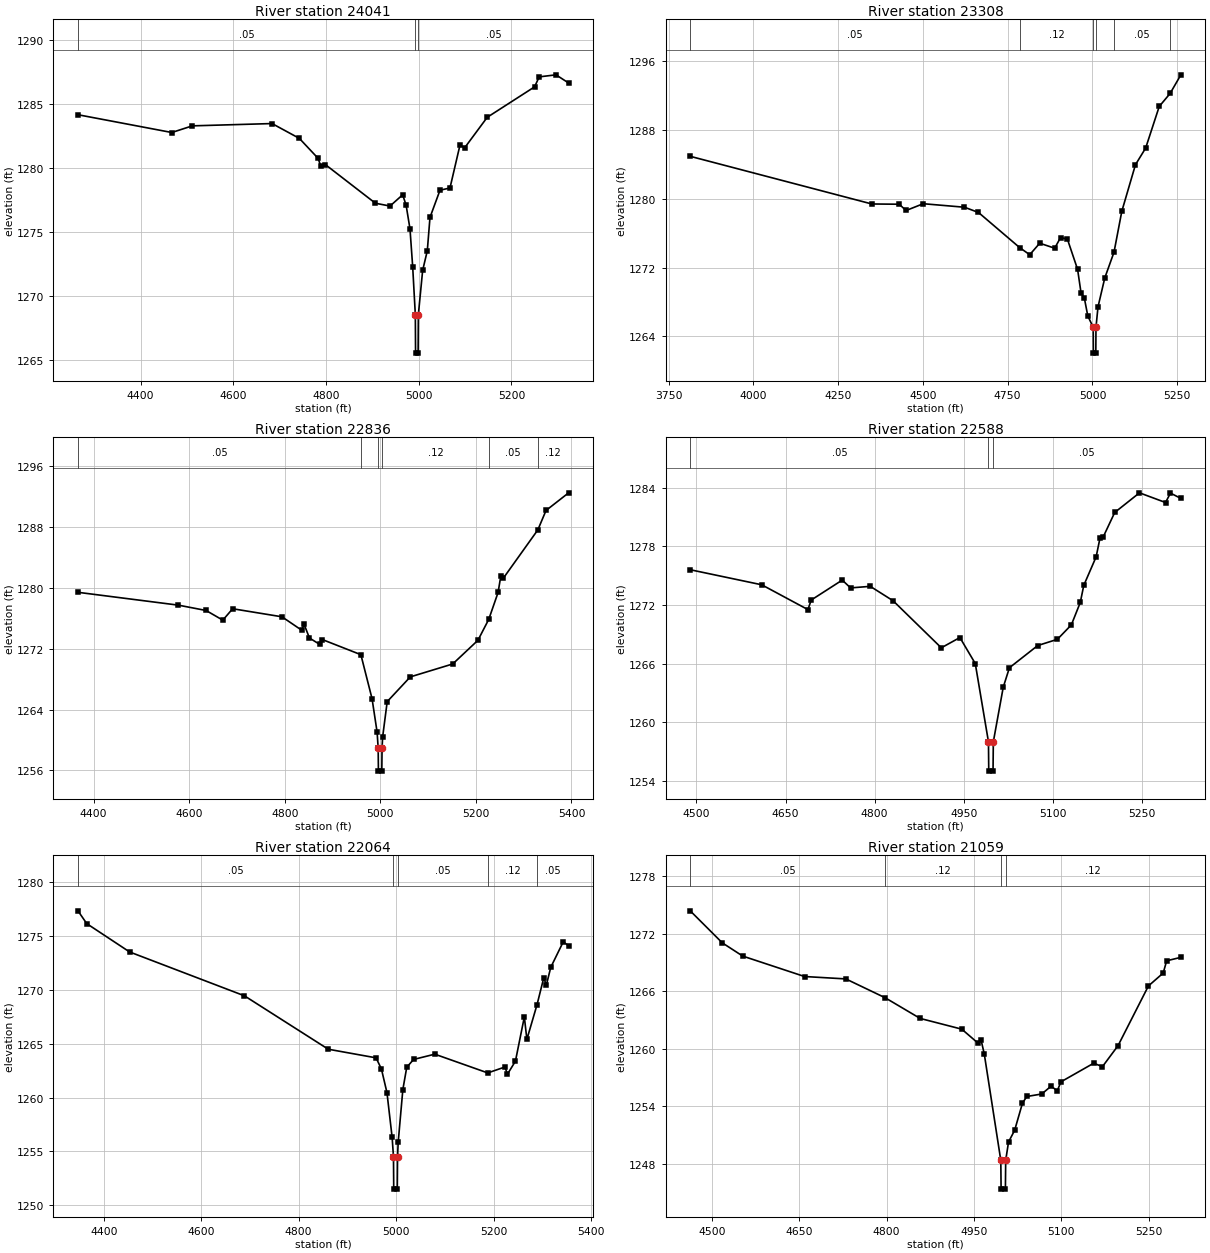
Type RM Length L Ch R = 1,24041,733,733,733
BEGIN DESCRIPTION:
HONDO CREEK 47.0
END DESCRIPTION:
XS GIS Cut Line= 3
      2815914.93     10187875.07      2815437.49     10187960.15
      2815151.03     10188456.68
#Sta/Elev= 30
  4265.1 1284.17  4467.5 1282.78  4511.8 1283.30  4683.7 1283.48  4742.6 1282.32
  4783.0 1280.76  4788.8 1280.15  4798.8 1280.27  4906.6 1277.25  4938.1 1277.03
  4965.4 1277.91  4972.8 1277.10  4981.2 1275.24  4987.0 1272.28  4992.7 1268.53
  4993.2 1265.53  4998.7 1265.53  4999.2 1268.53  5008.5 1272.00  5018.5 1273.53
  5024.3 1276.14  5045.9 1278.27  5067.4 1278.44  5089.0 1281.80  5099.0 1281.58
  5147.8 1283.97  5249.9 1286.35  5259.8 1287.13  5296.1 1287.29  5323.3 1286.65
#Mann=3,-1,0
  4265.1    0.05       0  4992.7    0.05       0  4999.2    0.05       0
Bank Sta=4992.7,4999.2
Exp/Cntr=0.3,0.1

Type RM Length L Ch R = 1,23308,472,472,472
BEGIN DESCRIPTION:
HONDO CREEK 46.0
END DESCRIPTION:
XS GIS Cut Line= 3
      2816234.33     10187722.29      2815175.34     10187552.16
      2814802.11     10187520.91
#Sta/Elev= 30
  3813.7 1284.95  4349.3 1279.40  4430.1 1279.37  4450.4 1278.64  4501.0 1279.43
  4622.6 1279.02  4663.9 1278.41  4785.0 1274.33  4815.0 1273.49  4844.5 1274.83
  4888.6 1274.25  4906.0 1275.49  4926.1 1275.31  4956.2 1271.78  4966.2 1269.08
  4976.2 1268.42  4986.3 1266.36  5002.3 1265.03  5002.8 1262.03  5009.9 1262.03
  5010.4 1265.03  5016.4 1267.42  5036.4 1270.79  5063.6 1273.79  5086.6 1278.55
  5126.8 1283.97  5156.9 1285.91  5197.0 1290.76  5229.0 1292.27  5260.8 1294.44
#Mann=6,-1,0
  3813.7    0.05       0  4785.0    0.12       0  5002.3    0.07       0
  5010.4    0.12       0  5063.6    0.05       0  5229.0    0.12       0
Bank Sta=5002.3,5010.4
Exp/Cntr=0.3,0.1

Type RM Length L Ch R = 1,22836,248,248,248
BEGIN DESCRIPTION:
HONDO CREEK 45.0
END DESCRIPTION:
XS GIS Cut Line= 3
      2815989.53     10187394.16      2815519.17     10187275.16
      2815005.70     10187103.12
#Sta/Elev= 30
  4367.3 1279.42  4577.6 1277.73  4635.4 1277.03  4670.4 1275.76  4691.0 1277.26
  4794.2 1276.20  4835.4 1274.44  4840.5 1275.21  4851.7 1273.41  4873.3 1272.57
  4878.6 1273.21  4959.3 1271.22  4982.7 1265.43  4993.3 1261.02  4995.5 1258.91
  4996.0 1255.91  5003.1 1255.91  5003.6 1258.91  5004.8 1260.39  5014.4 1265.05
  5062.7 1268.30  5151.5 1270.00  5204.2 1273.11  5226.9 1275.87  5246.4 1279.40
  5252.0 1281.53  5257.3 1281.27  5329.6 1287.63  5346.7 1290.18  5394.0 1292.50
#Mann=6,-1,0
  4367.3    0.05       0  4959.3    0.12       0  4995.5    0.07       0
  5003.6    0.12       0  5226.9    0.05       0  5329.6    0.12       0
Bank Sta=4995.5,5003.6
Exp/Cntr=0.3,0.1

Type RM Length L Ch R = 1,22588,524,524,524
BEGIN DESCRIPTION:
HONDO CREEK 44.0
END DESCRIPTION:
XS GIS Cut Line= 3
      2815914.33     10187167.67      2815829.85     10187104.24
      2815138.88     10186899.89
#Sta/Elev= 30
  4489.5 1275.60  4609.9 1274.06  4687.7 1271.52  4693.3 1272.50  4745.5 1274.54
  4759.5 1273.74  4792.7 1273.90  4831.2 1272.42  4912.3 1267.61  4943.6 1268.66
  4969.5 1266.00  4991.7 1257.99  4992.2 1254.99  4999.4 1254.99  4999.9 1257.99
  5016.6 1263.58  5027.0 1265.57  5074.6 1267.84  5107.8 1268.48  5131.3 1269.96
  5146.3 1272.25  5152.2 1274.00  5173.0 1276.92  5179.6 1278.87  5184.8 1278.94
  5204.3 1281.46  5246.0 1283.47  5289.8 1282.48  5298.2 1283.44  5315.7 1282.90
#Mann=3,-1,0
  4489.5    0.05       0  4991.7    0.05       0  4999.9    0.05       0
Bank Sta=4991.7,4999.9
Exp/Cntr=0.3,0.1

Type RM Length L Ch R = 1,22064,1005,1005,1005
BEGIN DESCRIPTION:
HONDO CREEK 43.0
END DESCRIPTION:
XS GIS Cut Line= 3
      2816262.10     10186789.99      2815605.89     10186489.66
      2815330.27     10186415.12
#Sta/Elev= 30
  4346.9 1277.34  4365.0 1276.15  4453.0 1273.52  4688.6 1269.45  4860.7 1264.49
  4958.8 1263.69  4969.8 1262.66  4981.2 1260.46  4991.8 1256.31  4994.6 1254.50
  4995.1 1251.50  5002.4 1251.50  5002.9 1254.50  5004.3 1255.88  5013.8 1260.74
  5021.8 1262.81  5035.8 1263.54  5079.4 1264.03  5188.1 1262.29  5223.4 1262.84
  5228.5 1262.17  5244.9 1263.38  5263.2 1267.49  5268.4 1265.40  5289.2 1268.62
  5303.1 1271.13  5308.3 1270.43  5317.4 1272.09  5343.0 1274.46  5354.1 1274.10
#Mann=5,-1,0
  4346.9    0.05       0  4994.6    0.05       0  5002.9    0.05       0
  5188.1    0.12       0  5289.2    0.05       0
Bank Sta=4994.6,5002.9
Exp/Cntr=0.3,0.1

Type RM Length L Ch R = 1,21059,509,509,509
BEGIN DESCRIPTION:
HONDO CREEK 42.0
END DESCRIPTION:
XS GIS Cut Line= 3
      2816348.94     10186227.50      2816017.35     10185921.95
      2815642.37     10185809.11
#Sta/Elev= 30
  4462.9 1274.40  4518.0 1271.06  4553.1 1269.68  4659.2 1267.55  4730.1 1267.30
  4797.8 1265.33  4857.7 1263.18  4929.2 1262.06  4957.0 1260.61  4962.2 1260.96
  4967.8 1259.48  4996.2 1248.38  4996.7 1245.38  5004.1 1245.38  5004.6 1248.38
  5009.5 1250.30  5020.0 1251.52  5033.4 1254.35  5040.9 1255.04  5066.5 1255.30
  5082.6 1256.12  5093.1 1255.63  5099.5 1256.57  5155.7 1258.51  5170.7 1258.15
  5197.5 1260.34  5249.7 1266.57  5275.0 1267.91  5281.0 1269.19  5305.4 1269.55
#Mann=4,-1,0
  4462.9    0.05       0  4797.8    0.12       0  4996.2    0.07       0
  5004.6    0.12       0
Bank Sta=4996.2,5004.6
Exp/Cntr=0.3,0.1

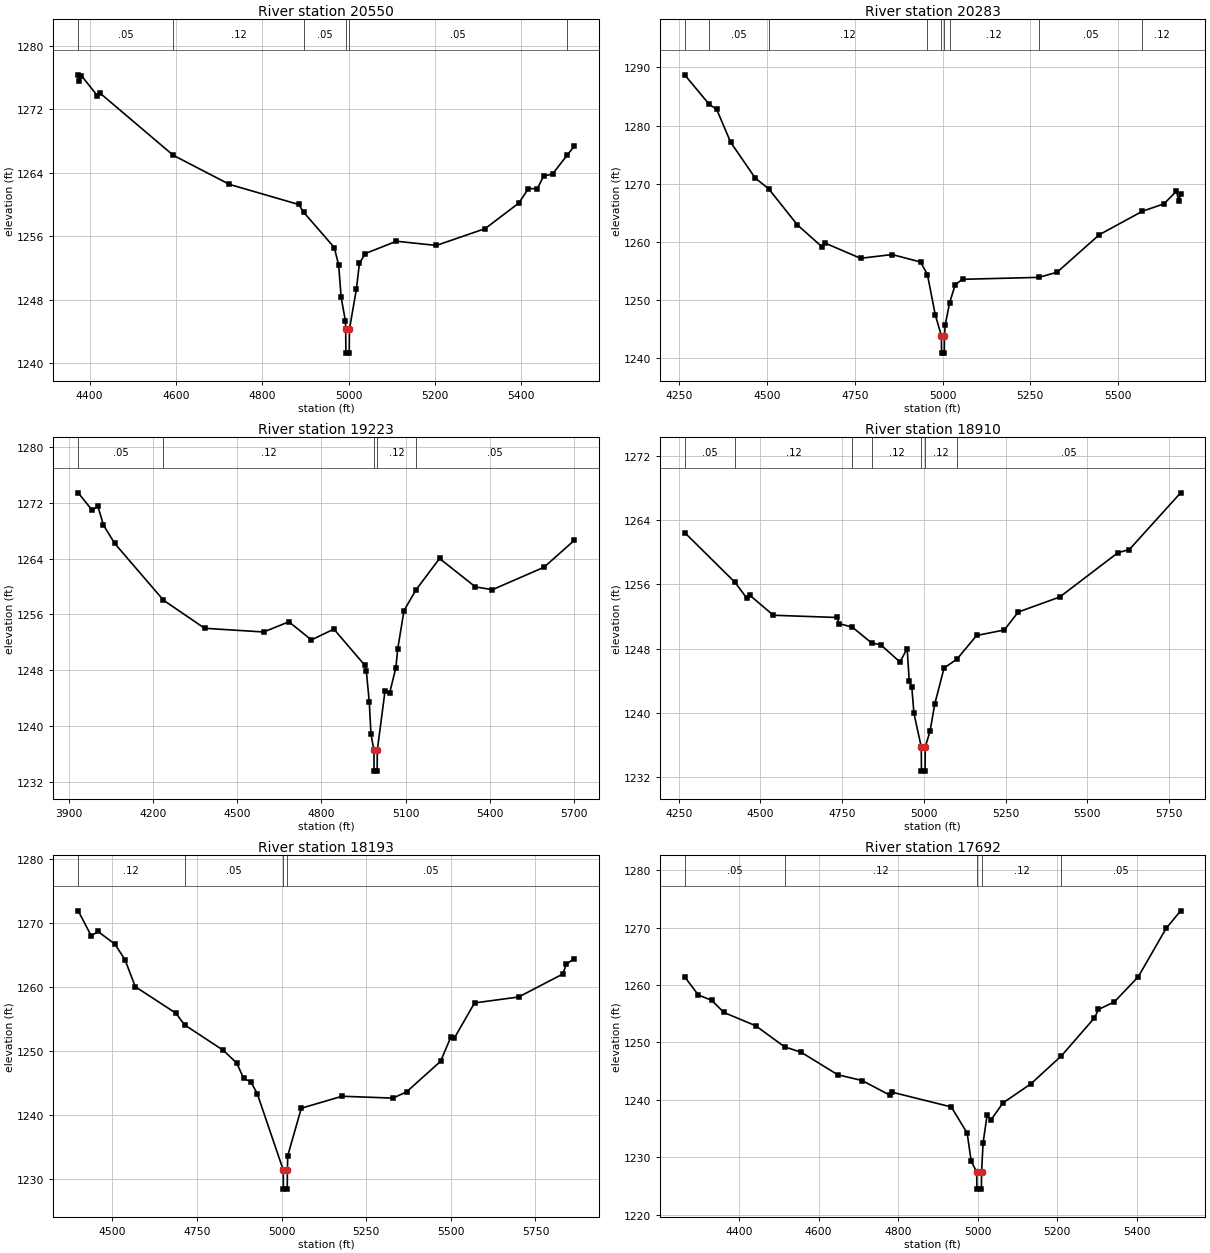
Type RM Length L Ch R = 1,20550,267,267,267
BEGIN DESCRIPTION:
HONDO CREEK 41.0
END DESCRIPTION:
XS GIS Cut Line= 3
      2816732.65     10185588.62      2816036.45     10185423.69
      2815705.66     10185703.14
#Sta/Elev= 30
  4373.7 1276.34  4375.8 1275.55  4381.0 1276.24  4418.1 1273.71  4423.2 1274.08
  4593.6 1266.21  4724.0 1262.53  4884.4 1260.00  4896.0 1259.01  4966.6 1254.58
  4976.9 1252.36  4982.6 1248.29  4992.3 1245.38  4993.1 1244.27  4993.6 1241.27
  5001.3 1241.27  5001.8 1244.27  5018.0 1249.35  5024.9 1252.59  5038.6 1253.82
  5110.7 1255.37  5203.0 1254.84  5316.1 1256.96  5394.1 1260.18  5416.2 1262.00
  5437.0 1261.98  5451.3 1263.58  5472.1 1263.83  5505.4 1266.18  5522.2 1267.32
#Mann=6,-1,0
  4373.7    0.05       0  4593.6    0.12       0  4896.0    0.05       0
  4993.1    0.05       0  5001.8    0.05       0  5505.4    0.12       0
Bank Sta=4993.1,5001.8
Exp/Cntr=0.3,0.1

Type RM Length L Ch R = 1,20283,1060,1060,1060
BEGIN DESCRIPTION:
HONDO CREEK 40.0
END DESCRIPTION:
XS GIS Cut Line= 3
      2816796.83     10185163.27      2816129.79     10185160.29
      2815634.60     10185718.84
#Sta/Elev= 30
  4264.8 1288.73  4334.8 1283.65  4355.9 1282.81  4395.9 1277.13  4466.0 1270.98
  4504.4 1269.12  4586.0 1262.94  4656.0 1259.17  4666.0 1259.78  4766.0 1257.19
  4856.0 1257.84  4937.1 1256.55  4956.7 1254.39  4979.1 1247.45  4996.5 1243.89
  4997.0 1240.89  5004.7 1240.89  5005.2 1243.89  5007.5 1245.76  5019.8 1249.52
  5035.9 1252.68  5056.8 1253.58  5273.7 1253.91  5326.1 1254.79  5446.6 1261.25
  5569.5 1265.28  5630.6 1266.55  5666.5 1268.72  5673.2 1267.02  5678.3 1268.22
#Mann=9,-1,0
  4264.8    0.12       0  4334.8    0.05       0  4504.4    0.12       0
  4956.7    0.05       0  4996.5    0.05       0  5005.2    0.05       0
  5019.8    0.12       0  5273.7    0.05       0  5569.5    0.12       0
Bank Sta=4996.5,5005.2
Exp/Cntr=0.3,0.1

Type RM Length L Ch R = 1,19223,313,313,313
BEGIN DESCRIPTION:
HONDO CREEK 39.0
END DESCRIPTION:
XS GIS Cut Line= 3
      2816805.65     10184803.11      2815824.64     10184816.05
      2815126.73     10184458.41
#Sta/Elev= 30
  3934.4 1273.43  3984.4 1270.91  4004.4 1271.51  4024.4 1268.78  4064.4 1266.16
  4237.9 1258.02  4384.4 1253.99  4594.4 1253.46  4684.4 1254.92  4764.4 1252.32
  4844.4 1253.87  4954.2 1248.70  4959.9 1247.86  4970.5 1243.40  4976.4 1238.81
  4987.0 1236.49  4987.5 1233.49  4998.5 1233.49  4999.0 1236.49  5026.7 1245.06
  5043.0 1244.72  5065.2 1248.35  5071.6 1251.01  5094.1 1256.53  5135.6 1259.44
  5220.6 1264.01  5348.2 1259.93  5408.7 1259.53  5592.4 1262.75  5699.7 1266.59
#Mann=5,-1,0
  3934.4    0.05       0  4237.9    0.12       0  4987.0    0.07       0
  4999.0    0.12       0  5135.6    0.05       0
Bank Sta=4987,4999
Exp/Cntr=0.3,0.1

Type RM Length L Ch R = 1,18910,717,717,717
BEGIN DESCRIPTION:
HONDO CREEK 38.0
END DESCRIPTION:
XS GIS Cut Line= 3
      2816639.98     10184754.86      2816023.64     10184612.49
      2815355.27     10184032.65
#Sta/Elev= 30
  4268.3 1262.46  4422.1 1256.27  4457.5 1254.34  4467.7 1254.65  4539.6 1252.16
  4734.6 1251.88  4741.1 1251.11  4781.2 1250.68  4840.7 1248.69  4868.0 1248.49
  4927.0 1246.33  4948.9 1248.00  4955.5 1243.92  4963.2 1243.21  4969.8 1239.92
  4992.2 1235.73  4992.7 1232.73  5003.8 1232.73  5004.3 1235.73  5019.2 1237.74
  5033.4 1241.09  5061.9 1245.58  5101.4 1246.69  5161.6 1249.64  5246.1 1250.32
  5288.9 1252.56  5416.1 1254.44  5593.7 1259.95  5628.8 1260.35  5785.7 1267.42
#Mann=7,-1,0
  4268.3    0.05       0  4422.1    0.12       0  4781.2    0.05       0
  4840.7    0.12       0  4992.2    0.07       0  5004.3    0.12       0
  5101.4    0.05       0
Bank Sta=4992.2,5004.3
Exp/Cntr=0.3,0.1

Type RM Length L Ch R = 1,18193,501,501,501
BEGIN DESCRIPTION:
HONDO CREEK 36.0
END DESCRIPTION:
XS GIS Cut Line= 3
      2816994.13     10184048.25      2816488.68     10184066.92
      2815532.31     10183985.75
#Sta/Elev= 30
  4398.7 1271.95  4437.2 1268.03  4457.2 1268.72  4507.2 1266.74  4537.2 1264.28
  4567.3 1260.09  4687.3 1255.95  4712.8 1254.13  4827.4 1250.14  4867.5 1248.13
  4887.5 1245.75  4908.5 1245.24  4927.6 1243.39  5004.6 1231.44  5005.1 1228.44
  5016.4 1228.44  5016.9 1231.44  5017.9 1233.66  5058.0 1241.09  5178.5 1242.96
  5329.0 1242.67  5369.2 1243.65  5469.5 1248.42  5499.6 1252.18  5509.7 1252.00
  5569.9 1257.55  5700.3 1258.48  5830.8 1262.07  5841.1 1263.61  5864.3 1264.46
#Mann=4,-1,0
  4398.7    0.12       0  4712.8    0.05       0  5004.6    0.05       0
  5016.9    0.05       0
Bank Sta=5004.6,5016.9
Exp/Cntr=0.3,0.1

Type RM Length L Ch R = 1,17692,397,397,397
BEGIN DESCRIPTION:
HONDO CREEK 35.0
END DESCRIPTION:
XS GIS Cut Line= 3
      2816942.01     10183735.75      2816318.78     10183603.81
      2815709.22     10183603.81
#Sta/Elev= 30
  4263.5 1261.42  4297.9 1258.25  4331.3 1257.33  4362.0 1255.21  4441.9 1252.90
  4514.5 1249.23  4556.2 1248.28  4648.2 1244.36  4709.5 1243.35  4779.6 1240.79
  4784.7 1241.32  4933.6 1238.75  4973.6 1234.18  4983.6 1229.31  4997.5 1227.43
  4998.0 1224.43  5009.3 1224.43  5009.8 1227.43  5013.6 1232.51  5023.6 1237.27
  5033.6 1236.51  5063.6 1239.45  5133.6 1242.77  5210.5 1247.65  5293.6 1254.27
  5303.6 1255.73  5343.6 1257.06  5403.6 1261.43  5473.6 1269.85  5510.1 1272.92
#Mann=5,-1,0
  4263.5    0.05       0  4514.5    0.12       0  4997.5    0.07       0
  5009.8    0.12       0  5210.5    0.05       0
Bank Sta=4997.5,5009.8
Exp/Cntr=0.3,0.1

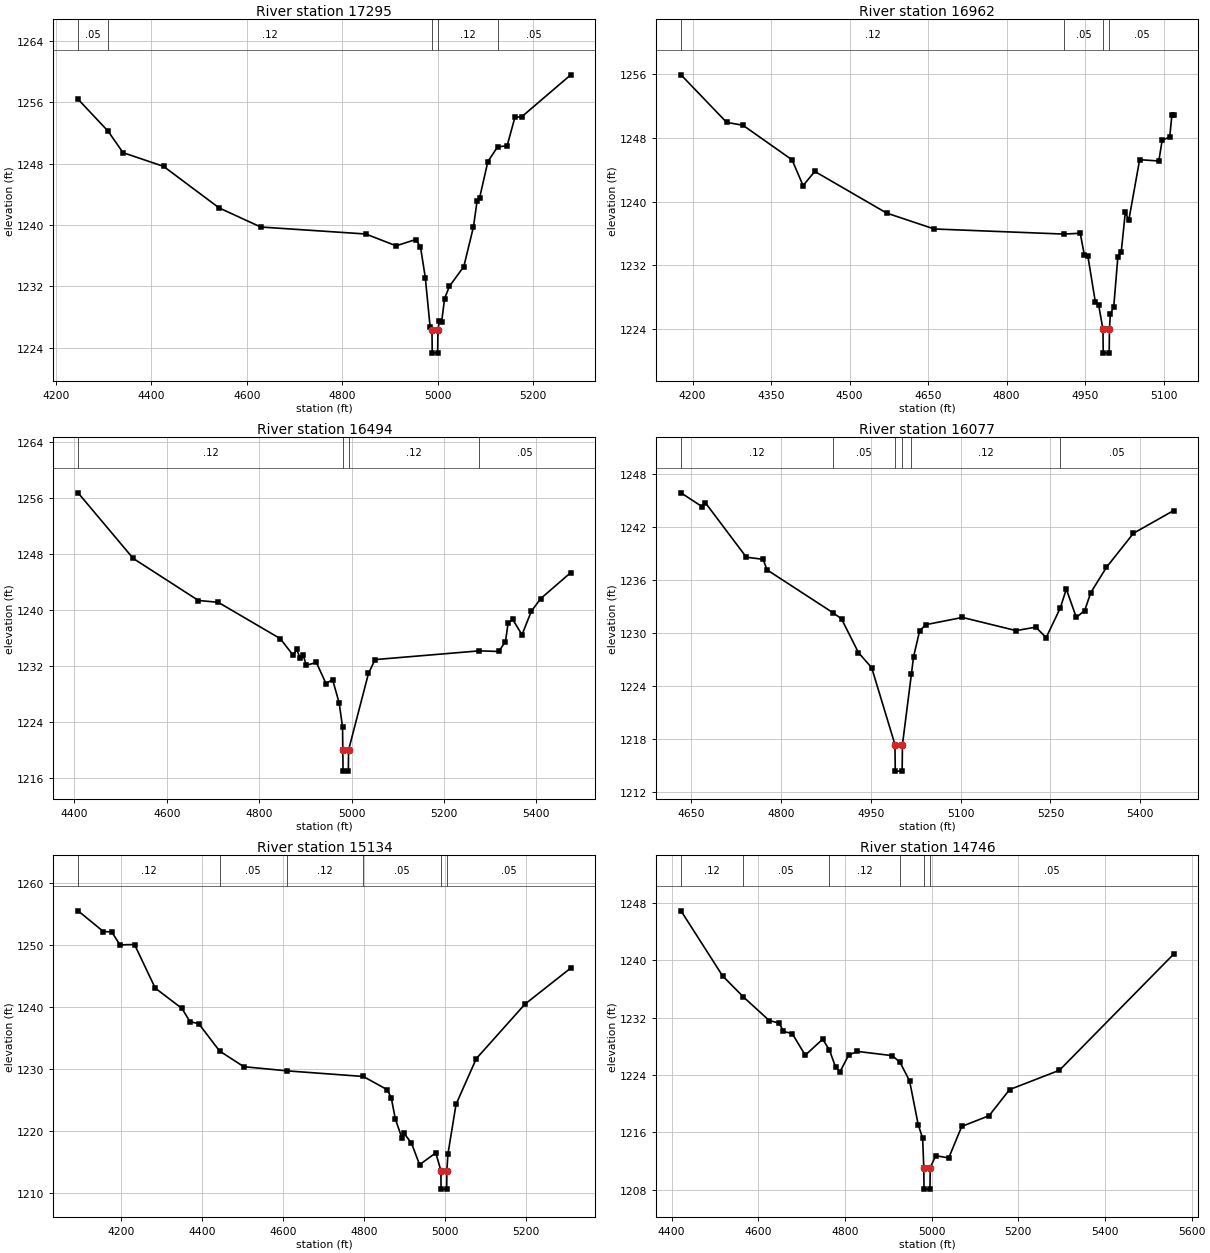
Type RM Length L Ch R = 1,17295,333,333,333
BEGIN DESCRIPTION:
HONDO CREEK 34.0
END DESCRIPTION:
XS GIS Cut Line= 3
      2816964.62     10183444.09      2816322.26     10183218.39
      2815973.33     10183173.26
#Sta/Elev= 30
  4246.4 1256.39  4309.4 1252.22  4340.7 1249.42  4425.5 1247.64  4542.1 1242.22
  4629.3 1239.73  4849.4 1238.82  4913.0 1237.28  4954.1 1238.10  4964.1 1237.15
  4974.2 1233.13  4984.3 1226.70  4988.2 1226.29  4988.7 1223.29  5000.1 1223.29
  5000.6 1226.29  5003.4 1227.42  5008.5 1227.40  5014.6 1230.40  5024.6 1231.98
  5054.9 1234.58  5075.1 1239.74  5082.7 1243.11  5087.8 1243.47  5105.3 1248.26
  5125.9 1250.19  5145.6 1250.31  5162.0 1254.03  5175.9 1254.08  5279.1 1259.57
#Mann=5,-1,0
  4246.4    0.05       0  4309.4    0.12       0  4988.2    0.07       0
  5000.6    0.12       0  5125.9    0.05       0
Bank Sta=4988.2,5000.6
Exp/Cntr=0.3,0.1

Type RM Length L Ch R = 1,16962,468,468,468
BEGIN DESCRIPTION:
HONDO CREEK 33.0
END DESCRIPTION:
XS GIS Cut Line= 3
      2817079.16     10183190.60      2816409.06     10182989.23
      2816256.26     10182801.70
#Sta/Elev= 30
  4177.9 1255.93  4265.1 1249.96  4296.4 1249.59  4390.1 1245.25  4411.2 1242.01
  4433.6 1243.79  4570.9 1238.56  4661.8 1236.56  4909.5 1235.92  4940.9 1236.02
  4948.9 1233.23  4955.3 1233.22  4969.7 1227.39  4976.1 1226.98  4984.3 1223.96
  4984.8 1220.96  4996.2 1220.96  4996.7 1223.96  4998.4 1225.87  5004.9 1226.78
  5012.8 1233.07  5019.2 1233.67  5027.1 1238.71  5033.6 1237.63  5054.4 1245.27
  5091.0 1245.10  5097.5 1247.72  5111.9 1248.12  5116.0 1250.88  5119.5 1250.88
#Mann=4,-1,0
  4177.9    0.12       0  4909.5    0.05       0  4984.3    0.05       0
  4996.7    0.05       0
Bank Sta=4984.3,4996.7
Exp/Cntr=0.3,0.1

Type RM Length L Ch R = 1,16494,417,417,417
BEGIN DESCRIPTION:
HONDO CREEK 32.0
END DESCRIPTION:
XS GIS Cut Line= 3
      2817126.06     10183001.36      2816633.02     10182544.78
      2816240.71     10182503.12
#Sta/Elev= 30
  4407.9 1256.80  4527.3 1247.43  4668.5 1241.42  4711.1 1241.17  4845.4 1235.98
  4873.8 1233.58  4881.1 1234.44  4888.0 1233.27  4895.3 1233.57  4902.1 1232.17
  4923.7 1232.57  4944.6 1229.56  4958.8 1230.13  4973.0 1226.79  4980.4 1223.37
  4981.0 1220.05  4981.5 1217.05  4992.9 1217.05  4993.4 1220.05  5036.5 1231.00
  5050.7 1232.98  5276.8 1234.23  5318.5 1234.14  5333.0 1235.56  5338.7 1238.17
  5348.7 1238.72  5368.8 1236.52  5388.9 1239.87  5409.1 1241.68  5474.4 1245.41
#Mann=4,-1,0
  4407.9    0.12       0  4981.0    0.07       0  4993.4    0.12       0
  5276.8    0.05       0
Bank Sta=4981,4993.4
Exp/Cntr=0.3,0.1

Type RM Length L Ch R = 1,16077,943,943,943
BEGIN DESCRIPTION:
HONDO CREEK 31.0
END DESCRIPTION:
XS GIS Cut Line= 3
      2817030.56     10182315.60      2816829.58     10182201.22
      2816250.01     10182320.69
#Sta/Elev= 30
  4632.9 1245.84  4667.8 1244.29  4673.5 1244.73  4742.1 1238.56  4770.1 1238.32
  4776.6 1237.13  4886.8 1232.28  4901.1 1231.58  4929.4 1227.76  4951.4 1226.07
  4990.3 1217.37  4990.8 1214.37  5002.3 1214.37  5002.8 1217.37  5017.8 1225.36
  5021.3 1227.28  5031.5 1230.23  5041.7 1230.93  5103.0 1231.75  5192.6 1230.26
  5225.5 1230.65  5242.9 1229.47  5266.6 1232.84  5276.5 1234.96  5293.2 1231.75
  5307.2 1232.53  5317.4 1234.56  5343.5 1237.41  5388.7 1241.27  5455.9 1243.84
#Mann=6,-1,0
  4632.9    0.12       0  4886.8    0.05       0  4990.3    0.05       0
  5002.8    0.05       0  5017.8    0.12       0  5266.6    0.05       0
Bank Sta=4990.3,5002.8
Exp/Cntr=0.3,0.1

Type RM Length L Ch R = 1,15134,388,388,388
BEGIN DESCRIPTION:
HONDO CREEK 30.0
END DESCRIPTION:
XS GIS Cut Line= 3
      2817237.18     10181320.83      2816617.39     10181444.09
      2816032.28     10181457.98
#Sta/Elev= 30
  4094.3 1255.56  4157.0 1252.21  4177.4 1252.16  4197.8 1250.06  4233.8 1250.12
  4284.9 1243.08  4350.7 1239.80  4371.1 1237.64  4392.3 1237.34  4443.8 1232.92
  4503.7 1230.38  4609.9 1229.71  4798.8 1228.80  4858.0 1226.67  4868.0 1225.37
  4878.0 1221.96  4894.4 1218.83  4899.4 1219.64  4918.0 1218.02  4938.0 1214.55
  4978.0 1216.46  4990.6 1213.60  4991.1 1210.60  5004.9 1210.60  5005.4 1213.60
  5008.0 1216.26  5028.0 1224.29  5078.0 1231.67  5198.1 1240.47  5311.5 1246.32
#Mann=6,-1,0
  4094.3    0.12       0  4443.8    0.05       0  4609.9    0.12       0
  4798.8    0.05       0  4990.6    0.03       0  5005.4    0.05       0
Bank Sta=4990.6,5005.4
Exp/Cntr=0.3,0.1

Type RM Length L Ch R = 1,14746,684,684,684
BEGIN DESCRIPTION:
HONDO CREEK 29.0
END DESCRIPTION:
XS GIS Cut Line= 3
      2817051.46     10181051.72      2816181.16     10181121.18
      2816055.67     10181353.14
#Sta/Elev= 30
  4421.8 1246.88  4517.9 1237.80  4565.3 1234.90  4625.5 1231.58  4648.3 1231.23
  4658.3 1230.06  4678.4 1229.77  4708.5 1226.75  4748.6 1228.98  4764.0 1227.52
  4778.7 1225.06  4788.7 1224.45  4808.8 1226.78  4828.9 1227.28  4909.1 1226.69
  4926.9 1225.78  4949.2 1223.17  4969.3 1217.02  4979.3 1215.20  4982.0 1211.08
  4982.5 1208.08  4996.3 1208.08  4996.8 1211.08  5009.7 1212.74  5039.5 1212.43
  5069.6 1216.82  5132.7 1218.32  5180.0 1221.96  5294.9 1224.65  5558.6 1240.85
#Mann=6,-1,0
  4421.8    0.12       0  4565.3    0.05       0  4764.0    0.12       0
  4926.9    0.05       0  4982.0    0.05       0  4996.8    0.05       0
Bank Sta=4982,4996.8
Exp/Cntr=0.3,0.1