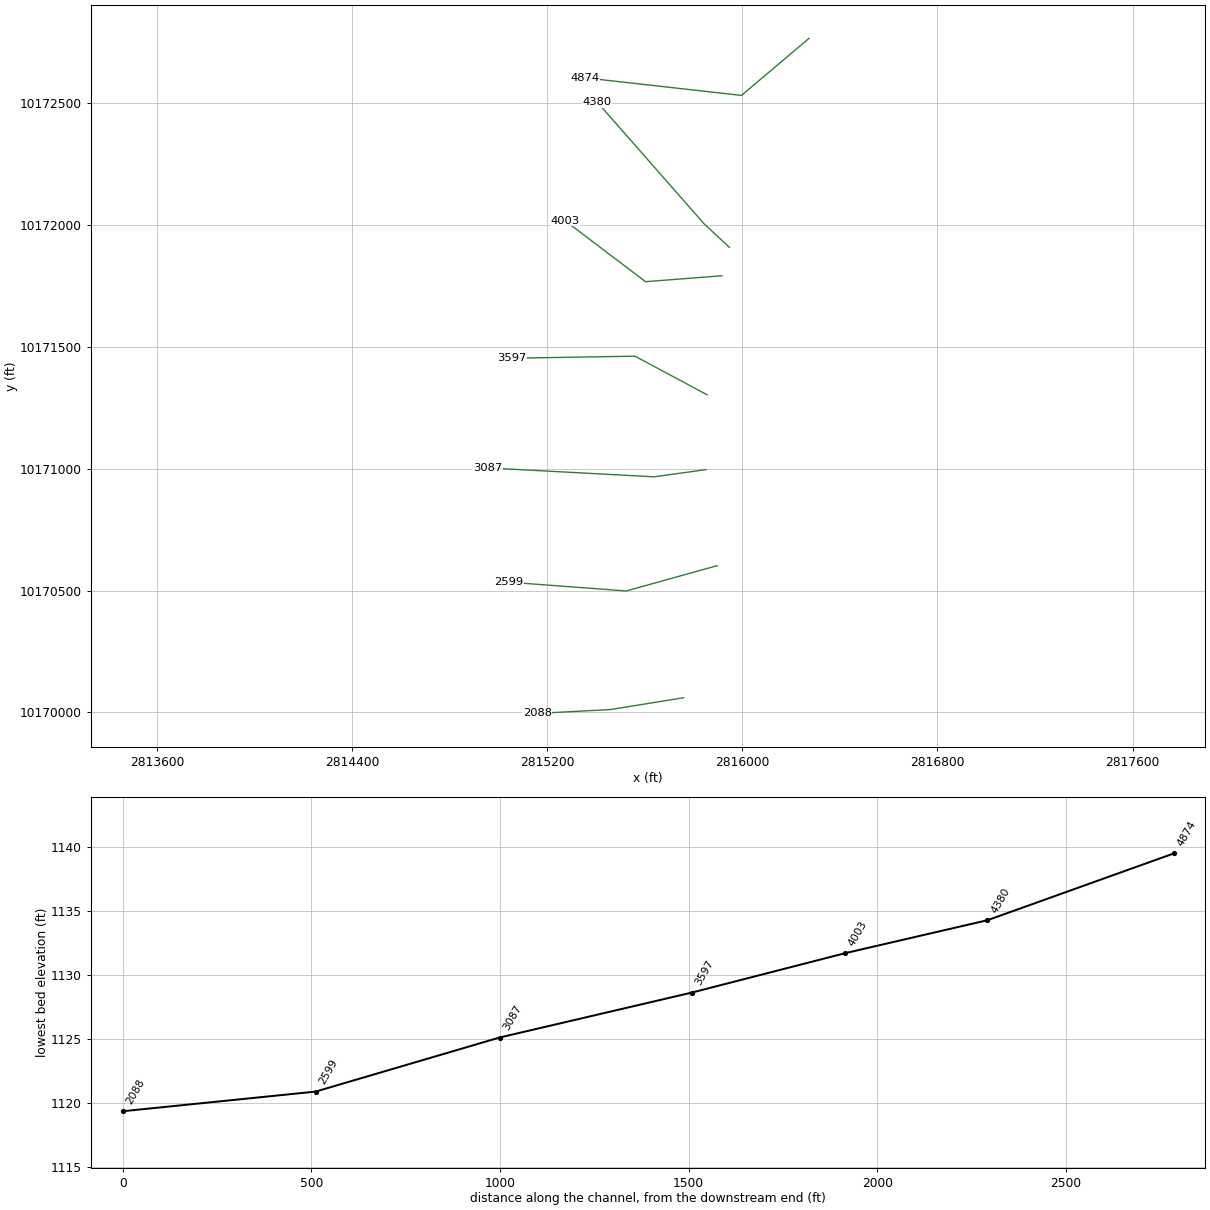
HEC-RAS study HONDO CREEK.prj: HONDO CREEK Base Level Engineering

--- HONDO CREEK.g01 (geometry) --- (continued)

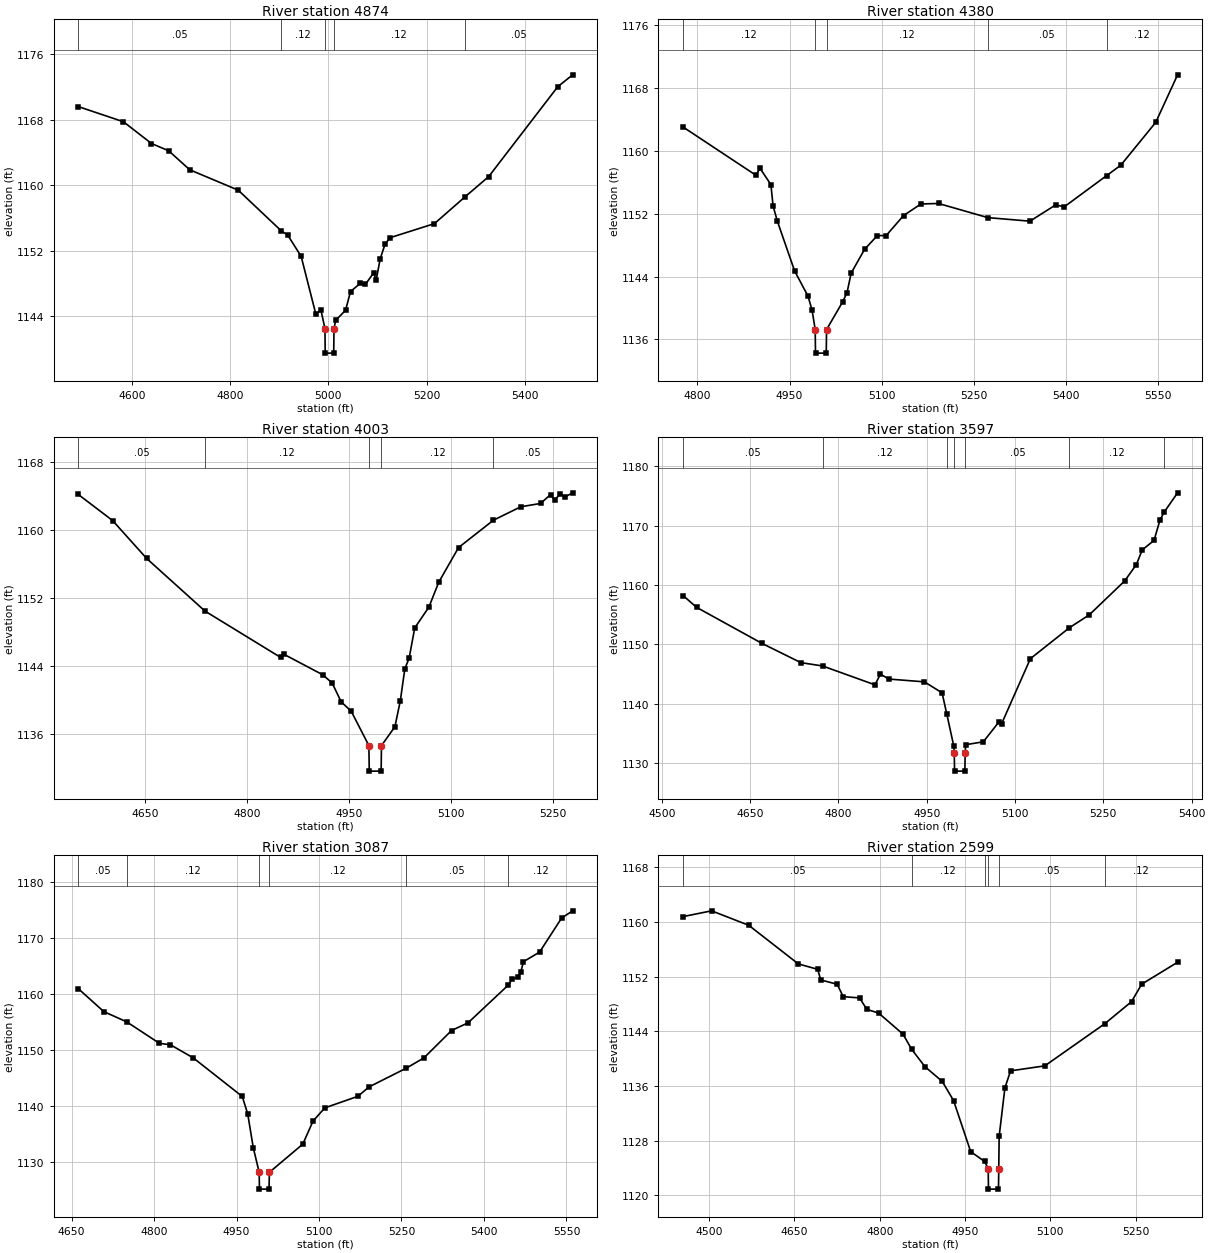
Type RM Length L Ch R = 1,4874,494,494,494
BEGIN DESCRIPTION:
HONDO CREEK 7.0
END DESCRIPTION:
XS GIS Cut Line= 3
      2816273.64     10172765.27      2815996.83     10172531.17
      2815355.69     10172603.11
#Sta/Elev= 30
  4490.1 1169.59  4582.1 1167.74  4639.3 1165.08  4674.4 1164.19  4717.3 1161.87
  4816.1 1159.38  4903.5 1154.43  4917.1 1153.88  4944.4 1151.29  4974.5 1144.19
  4984.6 1144.76  4992.9 1142.47  4993.4 1139.47  5010.8 1139.47  5011.3 1142.47
  5014.8 1143.47  5034.9 1144.71  5045.0 1146.99  5065.1 1148.01  5075.2 1147.86
  5092.3 1149.28  5097.3 1148.38  5105.4 1150.97  5115.4 1152.78  5125.5 1153.57
  5216.0 1155.29  5277.6 1158.52  5326.7 1161.04  5467.6 1172.03  5497.8 1173.47
#Mann=5,-1,0
  4490.1    0.05       0  4903.5    0.12       0  4992.9    0.07       0
  5011.3    0.12       0  5277.6    0.05       0
Bank Sta=4992.9,5011.3
Exp/Cntr=0.3,0.1

Type RM Length L Ch R = 1,4380,377,377,377
BEGIN DESCRIPTION:
HONDO CREEK 6.0
END DESCRIPTION:
XS GIS Cut Line= 3
      2815947.27     10171907.62      2815842.82     10172005.15
      2815405.69     10172503.10
#Sta/Elev= 30
  4776.7 1163.02  4894.9 1156.91  4902.0 1157.76  4919.6 1155.71  4923.2 1152.98
  4930.2 1151.04  4958.3 1144.71  4980.1 1141.51  4986.8 1139.70  4991.8 1137.26
  4992.3 1134.26  5009.8 1134.26  5010.3 1137.26  5036.6 1140.79  5043.7 1141.97
  5050.4 1144.44  5072.2 1147.46  5093.1 1149.22  5107.3 1149.21  5135.7 1151.76
  5164.2 1153.24  5192.7 1153.30  5273.2 1151.50  5341.7 1151.05  5383.4 1153.11
  5397.7 1152.88  5466.7 1156.85  5489.7 1158.17  5546.6 1163.62  5582.2 1169.67
#Mann=5,-1,0
  4776.7    0.12       0  4991.8    0.07       0  5010.3    0.12       0
  5273.2    0.05       0  5466.7    0.12       0
Bank Sta=4991.8,5010.3
Exp/Cntr=0.3,0.1

Type RM Length L Ch R = 1,4003,406,406,406
BEGIN DESCRIPTION:
HONDO CREEK 5.0
END DESCRIPTION:
XS GIS Cut Line= 3
      2815916.03     10171791.31      2815603.51     10171767.00
      2815273.61     10172017.03
#Sta/Elev= 30
  4551.4 1164.24  4601.9 1161.17  4652.0 1156.71  4737.8 1150.52  4849.1 1145.07
  4854.1 1145.43  4911.2 1143.02  4924.9 1142.06  4938.3 1139.83  4952.9 1138.75
  4979.0 1134.69  4979.5 1131.69  4997.0 1131.69  4997.5 1134.69  5017.3 1136.92
  5025.2 1139.96  5031.9 1143.73  5038.2 1144.98  5046.4 1148.53  5067.3 1150.99
  5081.8 1153.92  5110.9 1157.99  5162.2 1161.21  5202.5 1162.79  5231.6 1163.18
  5246.2 1164.22  5252.4 1163.57  5260.7 1164.34  5267.0 1163.93  5278.8 1164.43
#Mann=5,-1,0
  4551.4    0.05       0  4737.8    0.12       0  4979.0    0.07       0
  4997.5    0.12       0  5162.2    0.05       0
Bank Sta=4979,4997.5
Exp/Cntr=0.3,0.1

Type RM Length L Ch R = 1,3597,510,510,510
BEGIN DESCRIPTION:
HONDO CREEK 4.0
END DESCRIPTION:
XS GIS Cut Line= 3
      2815855.69     10171303.11      2815560.10     10171461.45
      2815055.70     10171453.11
#Sta/Elev= 30
  4536.3 1158.19  4559.0 1156.22  4670.4 1150.13  4736.2 1146.90  4773.0 1146.34
  4862.1 1143.16  4871.3 1144.95  4886.1 1144.13  4946.1 1143.66  4976.1 1141.81
  4984.1 1138.23  4996.1 1132.77  4996.8 1131.62  4997.3 1128.62  5014.8 1128.62
  5015.3 1131.62  5016.1 1133.07  5046.1 1133.56  5072.3 1136.86  5077.3 1136.62
  5126.1 1147.57  5192.5 1152.79  5226.1 1154.95  5286.1 1160.65  5306.1 1163.42
  5316.1 1165.90  5336.1 1167.49  5346.1 1170.89  5353.0 1172.21  5376.1 1175.51
#Mann=7,-1,0
  4536.3    0.05       0  4773.0    0.12       0  4984.1    0.05       0
  4996.8    0.05       0  5015.3    0.05       0  5192.5    0.12       0
  5353.0    0.05       0
Bank Sta=4996.8,5015.3
Exp/Cntr=0.3,0.1

Type RM Length L Ch R = 1,3087,488,488,488
BEGIN DESCRIPTION:
HONDO CREEK 3.0
END DESCRIPTION:
XS GIS Cut Line= 3
      2815851.76     10170996.17      2815638.23     10170966.66
      2814955.66     10171003.11
#Sta/Elev= 30
  4662.2 1160.91  4708.7 1156.80  4750.4 1154.97  4809.7 1151.15  4829.9 1150.88
  4871.2 1148.55  4960.4 1141.66  4970.4 1138.53  4980.5 1132.49  4991.2 1128.11
  4991.7 1125.11  5009.2 1125.11  5009.7 1128.11  5070.6 1133.15  5089.1 1137.26
  5110.6 1139.62  5170.7 1141.68  5190.8 1143.35  5259.0 1146.72  5290.9 1148.55
  5341.0 1153.43  5371.0 1154.80  5444.0 1161.52  5451.1 1162.60  5461.1 1162.90
  5466.8 1163.82  5471.8 1165.72  5501.2 1167.44  5541.3 1173.52  5561.3 1174.80
#Mann=6,-1,0
  4662.2    0.05       0  4750.4    0.12       0  4991.2    0.07       0
  5009.7    0.12       0  5259.0    0.05       0  5444.0    0.12       0
Bank Sta=4991.2,5009.7
Exp/Cntr=0.3,0.1

Type RM Length L Ch R = 1,2599,511,511,511
BEGIN DESCRIPTION:
HONDO CREEK 2.0
END DESCRIPTION:
XS GIS Cut Line= 3
      2815896.89     10170602.07      2815524.24     10170498.38
      2815042.79     10170534.36
#Sta/Elev= 30
  4454.3 1160.80  4504.3 1161.64  4569.7 1159.52  4656.8 1153.87  4691.0 1153.07
  4696.2 1151.52  4725.2 1150.89  4735.8 1149.07  4764.6 1148.89  4777.3 1147.21
  4798.1 1146.67  4841.1 1143.57  4856.0 1141.38  4879.8 1138.80  4909.9 1136.67
  4929.9 1133.86  4960.0 1126.38  4984.5 1124.94  4990.8 1123.89  4991.3 1120.89
  5008.9 1120.89  5009.4 1123.89  5010.1 1128.63  5020.2 1135.72  5030.2 1138.21
  5090.4 1138.94  5196.0 1145.12  5242.9 1148.34  5260.8 1150.90  5323.9 1154.11
#Mann=6,-1,0
  4454.3    0.05       0  4856.0    0.12       0  4984.5    0.05       0
  4990.8    0.05       0  5009.4    0.05       0  5196.0    0.12       0
Bank Sta=4990.8,5009.4
Exp/Cntr=0.3,0.1

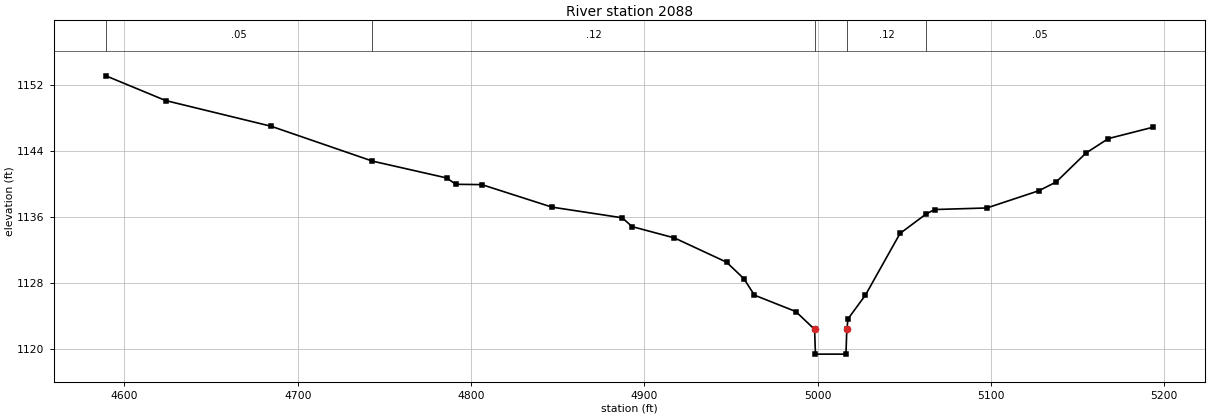
Type RM Length L Ch R = 1,2088,0,0,0
BEGIN DESCRIPTION:
HONDO CREEK 1.0
END DESCRIPTION:
XS GIS Cut Line= 3
      2815759.78     10170060.41      2815459.41     10170011.80
      2815159.90     10169996.21
#Sta/Elev= 30
  4589.3 1153.10  4623.8 1150.10  4684.6 1146.99  4743.1 1142.76  4785.9 1140.72
  4791.2 1139.95  4806.2 1139.91  4846.7 1137.18  4887.2 1135.89  4892.9 1134.82
  4917.3 1133.45  4947.4 1130.51  4957.4 1128.51  4963.5 1126.51  4987.4 1124.52
  4998.2 1122.36  4998.7 1119.36  5016.3 1119.36  5016.8 1122.36  5017.5 1123.64
  5027.5 1126.50  5047.5 1133.99  5062.5 1136.34  5067.5 1136.89  5097.6 1137.08
  5127.6 1139.17  5137.6 1140.23  5154.8 1143.74  5167.7 1145.49  5193.5 1146.87
#Mann=5,-1,0
  4589.3    0.05       0  4743.1    0.12       0  4998.2    0.07       0
  5016.8    0.12       0  5062.5    0.05       0
Bank Sta=4998.2,5016.8
Exp/Cntr=0.3,0.1

Chan Stop Cuts=-1