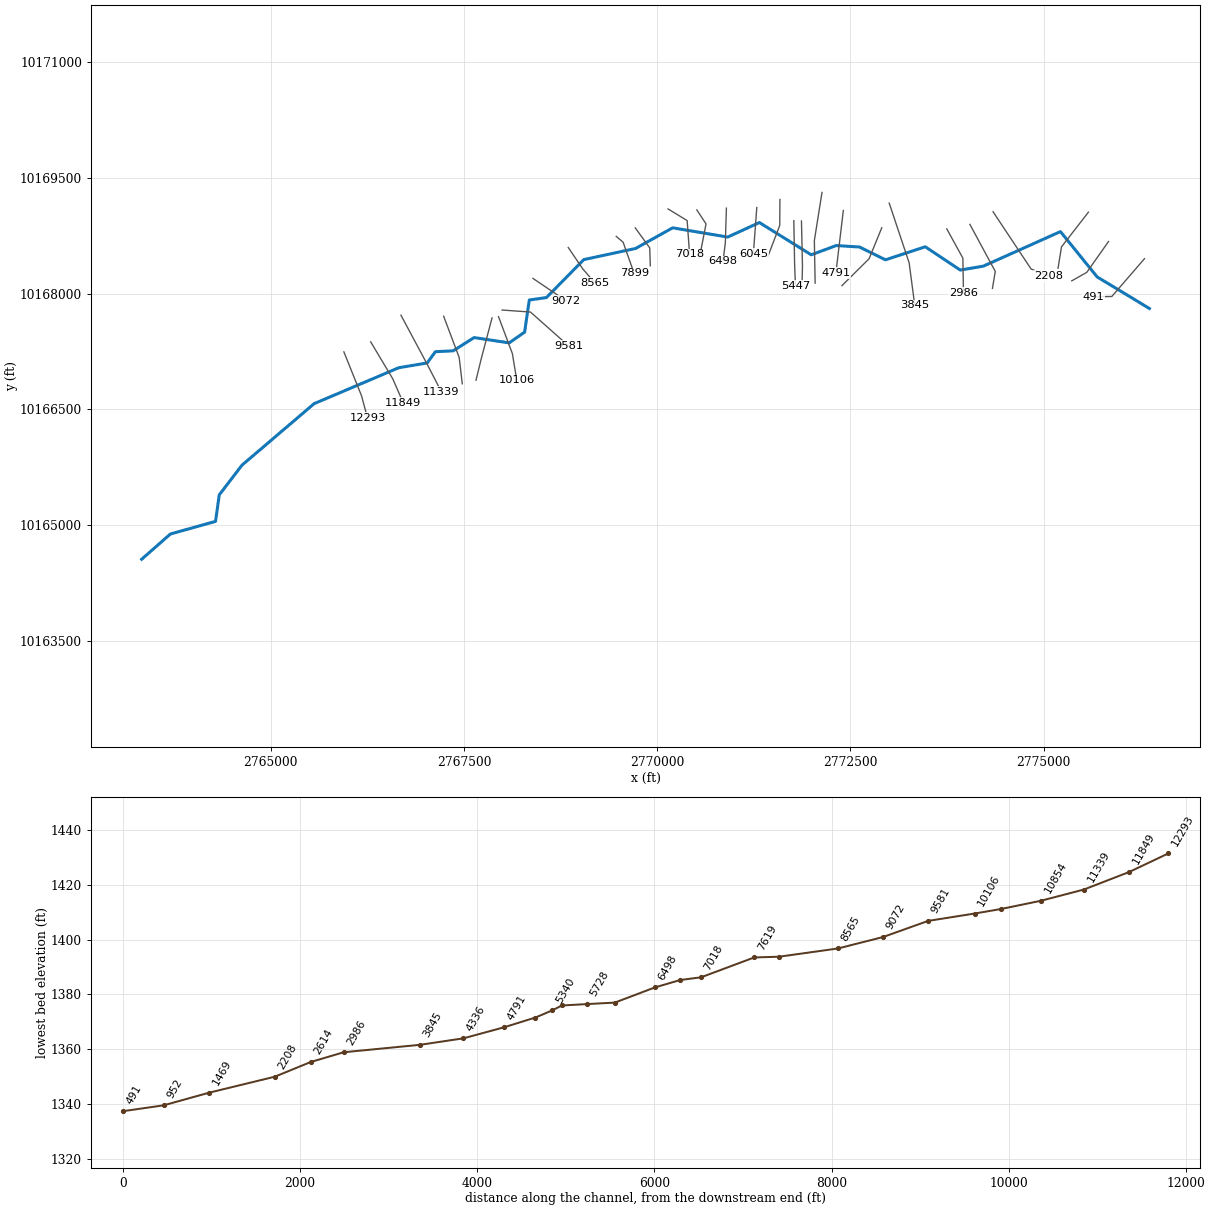
--- NORTH HELMS CREEK.prj (project) ---

Proj Title=NORTH HELMS CREEK Base Level Engineering
Current Plan=p01
Default Exp/Contr=0.3,0.1
English Units
Geom File=g01
Flow File=f01
Plan File=p01
BEGIN DESCRIPTION:
NORTH HELMS CREEK
END DESCRIPTION:

--- NORTH HELMS CREEK.p01 (plan) ---

Plan Title=Multiple Run
Short Identifier=Multiple
Geom File=g01
Flow File=f01
Subcritical Flow
K Sum by GR= 0
Std Step Tol= 0.01
Critical Tol= 0.01
Num of Std Step Trials= 20
Max Error Tol= 0.3
Flow Tol Ratio= 0.001
Split Flow NTrial= 30
Split Flow Tol= 0.02
Split Flow Ratio= 0.02
Log Output Level= 0
Friction Slope Method= 1
Unsteady Friction Slope Method= 2
Unsteady Bridges Friction Slope Method= 1
Parabolic Critical Depth
Global Vel Dist=  1 , 1 , 1
Global Log Level= 0
CheckData=True
Encroach Param= -1, 0, 0, 0
BEGIN DESCRIPTION:
Multiple Run
END DESCRIPTION:

--- NORTH HELMS CREEK.f01 (steady flow) ---

Flow Title=Multiple
Number of Profiles=7
Profile Names=10-year,25-year,50-year,1pct_min,100-year,1pct_plu,500-year
River Rch & RM= NORTH HELMS CREE,Reach-1,12293
     108     219     352     187     565    1705    1549
River Rch & RM= NORTH HELMS CREE,Reach-1,5150
     125     260     421     225     680    2052    1889
River Rch & RM= NORTH HELMS CREE,Reach-1,1469
     159     338     554     299     903    2726    2554
Boundary for River Rch & Prof#=NORTH HELMS CREE,Reach-1,1
Up Type=0
Dn Type=3
Dn Slope=0.005
Boundary for River Rch & Prof#=NORTH HELMS CREE,Reach-1,2
Up Type=0
Dn Type=3
Dn Slope=0.005
Boundary for River Rch & Prof#=NORTH HELMS CREE,Reach-1,3
Up Type=0
Dn Type=3
Dn Slope=0.005
Boundary for River Rch & Prof#=NORTH HELMS CREE,Reach-1,4
Up Type=0
Dn Type=3
Dn Slope=0.005
Boundary for River Rch & Prof#=NORTH HELMS CREE,Reach-1,5
Up Type=0
Dn Type=3
Dn Slope=0.005
Boundary for River Rch & Prof#=NORTH HELMS CREE,Reach-1,6
Up Type=0
Dn Type=3
Dn Slope=0.005
Boundary for River Rch & Prof#=NORTH HELMS CREE,Reach-1,7
Up Type=0
Dn Type=3
Dn Slope=0.005

--- NORTH HELMS CREEK.g01 (geometry) ---

Geom Title=Existing Conditions

River Reach=NORTH HELMS CREE,Reach-1
Reach XY= 30
      2763328.75     10164556.00      2763700.25     10164883.00
      2764284.50     10165047.00      2764332.75     10165391.00
      2764627.00     10165776.00      2765560.25     10166573.00
      2766656.00     10167039.00      2767023.50     10167101.00
      2767129.50     10167247.00      2767359.50     10167258.00
      2767630.75     10167430.00      2768084.00     10167361.00
      2768284.00     10167500.00      2768344.50     10167917.00
      2768567.00     10167949.00      2769050.00     10168441.00
      2769719.50     10168585.00      2770200.50     10168853.00
      2770911.50     10168733.00      2771322.25     10168921.00
      2771993.25     10168503.00      2772316.25     10168623.00
      2772618.00     10168604.00      2772954.00     10168438.00
      2773468.50     10168607.00      2773921.75     10168305.00
      2774220.25     10168356.00      2775218.00     10168804.00
      2775692.25     10168217.00      2776369.00     10167807.00

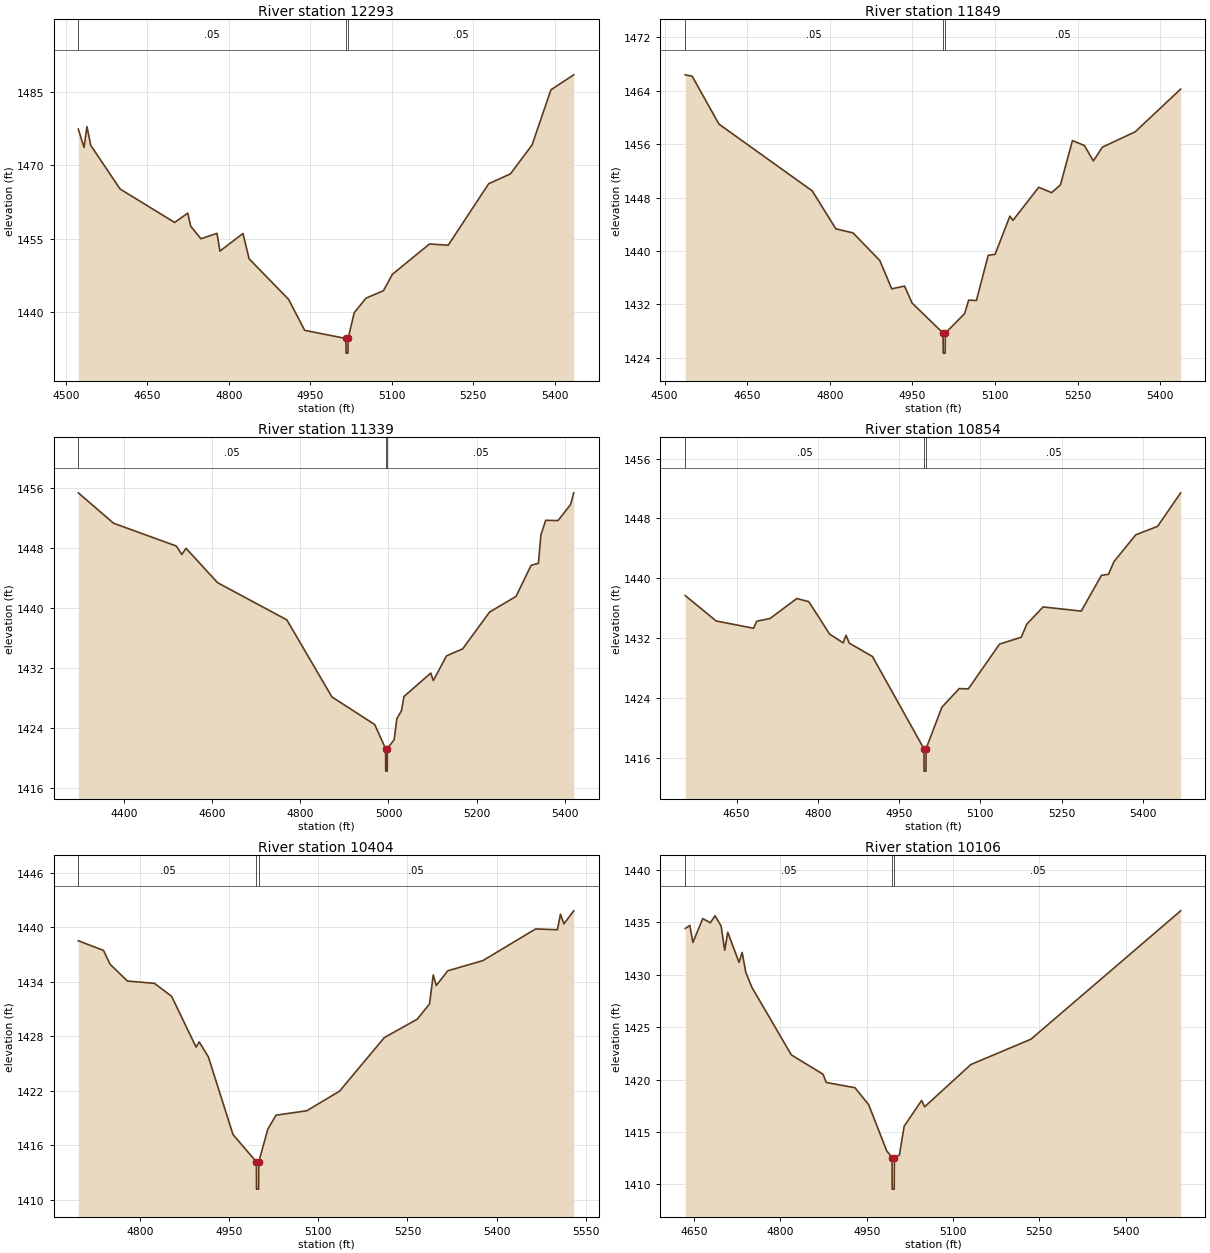
Type RM Length L Ch R = 1,12293,444,444,444
BEGIN DESCRIPTION:
NORTH HELMS CREEK 25.0
END DESCRIPTION:
XS GIS Cut Line= 3
      2765945.38     10167244.46      2766173.10     10166676.82
      2766251.43     10166386.83
#Sta/Elev= 30
  4523.0 1477.42  4533.5 1473.66  4538.9 1477.92  4546.0 1474.07  4599.9 1465.14
  4700.3 1458.29  4724.5 1460.20  4729.9 1457.53  4748.7 1454.95  4778.3 1456.06
  4783.7 1452.42  4826.1 1456.03  4837.5 1450.83  4910.1 1442.54  4939.7 1436.19
  5015.7 1434.52  5015.9 1431.52  5019.4 1431.52  5019.7 1434.52  5030.9 1439.80
  5052.7 1442.79  5084.7 1444.30  5101.1 1447.66  5169.5 1453.88  5203.9 1453.62
  5278.5 1466.23  5318.4 1468.23  5358.3 1474.16  5393.0 1485.46  5435.0 1488.53
#Mann=3,-1,0
  4523.0    0.05       0  5015.7    0.05       0  5019.7    0.05       0
Bank Sta=5015.7,5019.7
Exp/Cntr=0.3,0.1

Type RM Length L Ch R = 1,11849,510,510,510
BEGIN DESCRIPTION:
NORTH HELMS CREEK 24.0
END DESCRIPTION:
XS GIS Cut Line= 3
      2766291.96     10167375.12      2766578.32     10166894.50
      2766713.97     10166583.01
#Sta/Elev= 30
  4537.6 1466.40  4550.2 1466.19  4598.8 1459.02  4768.2 1449.01  4811.0 1443.33
  4842.2 1442.72  4890.9 1438.57  4912.4 1434.34  4935.7 1434.76  4949.3 1432.22
  5005.7 1427.71  5005.9 1424.71  5009.4 1424.71  5009.7 1427.71  5044.7 1430.63
  5052.1 1432.66  5066.1 1432.59  5087.5 1439.36  5100.0 1439.51  5126.9 1445.23
  5132.4 1444.60  5179.2 1449.55  5202.7 1448.75  5218.6 1449.91  5240.4 1456.55
  5262.2 1455.81  5278.4 1453.50  5294.9 1455.57  5354.2 1457.86  5436.8 1464.26
#Mann=3,-1,0
  4537.6    0.05       0  5005.7    0.05       0  5009.7    0.05       0
Bank Sta=5005.7,5009.7
Exp/Cntr=0.3,0.1

Type RM Length L Ch R = 1,11339,485,485,485
BEGIN DESCRIPTION:
NORTH HELMS CREEK 23.0
END DESCRIPTION:
XS GIS Cut Line= 3
      2766683.83     10167719.99      2767015.00     10167100.00
      2767207.20     10166726.78
#Sta/Elev= 30
  4297.1 1455.39  4377.0 1451.34  4519.3 1448.30  4531.6 1447.17  4541.2 1448.00
  4612.7 1443.42  4769.7 1438.46  4871.8 1428.20  4968.9 1424.51  4993.4 1421.31
  4993.7 1418.31  4997.2 1418.31  4997.4 1421.31  5012.9 1422.51  5019.0 1425.32
  5029.4 1426.35  5035.1 1428.25  5095.9 1431.38  5101.6 1430.37  5131.5 1433.67
  5168.1 1434.60  5229.0 1439.50  5289.0 1441.59  5323.3 1445.74  5339.8 1446.00
  5345.4 1449.79  5356.3 1451.73  5384.1 1451.69  5412.7 1453.83  5419.8 1455.38
#Mann=3,-1,0
  4297.1    0.05       0  4993.4    0.05       0  4997.4    0.05       0
Bank Sta=4993.4,4997.4
Exp/Cntr=0.3,0.1

Type RM Length L Ch R = 1,10854,450,450,450
BEGIN DESCRIPTION:
NORTH HELMS CREEK 22.0
END DESCRIPTION:
XS GIS Cut Line= 3
      2767236.38     10167706.66      2767437.33     10167172.46
      2767477.52     10166830.86
#Sta/Elev= 30
  4555.0 1437.69  4612.2 1434.29  4681.2 1433.32  4687.0 1434.26  4711.5 1434.62
  4761.2 1437.30  4783.2 1436.87  4821.7 1432.53  4846.6 1431.37  4851.9 1432.38
  4857.9 1431.33  4900.7 1429.54  4995.7 1417.21  4996.0 1414.21  4999.5 1414.21
  4999.7 1417.21  5028.9 1422.76  5060.9 1425.25  5077.7 1425.21  5135.2 1431.19
  5175.4 1432.12  5185.5 1433.85  5215.7 1436.17  5286.2 1435.61  5323.5 1440.40
  5336.5 1440.53  5346.6 1442.23  5386.9 1445.82  5427.2 1446.95  5469.7 1451.43
#Mann=3,-1,0
  4555.0    0.05       0  4995.7    0.05       0  4999.7    0.05       0
Bank Sta=4995.7,4999.7
Exp/Cntr=0.3,0.1

Type RM Length L Ch R = 1,10404,298,298,298
BEGIN DESCRIPTION:
NORTH HELMS CREEK 21.0
END DESCRIPTION:
XS GIS Cut Line= 3
      2767862.65     10167684.86      2767722.10     10167152.92
      2767655.26     10166877.10
#Sta/Elev= 30
  4696.0 1438.50  4738.4 1437.44  4749.5 1435.92  4778.7 1434.07  4824.1 1433.82
  4853.0 1432.40  4894.3 1426.81  4899.5 1427.38  4915.0 1425.73  4956.4 1417.20
  4995.8 1414.20  4996.0 1411.20  4999.5 1411.20  4999.8 1414.20  5015.1 1417.80
  5028.8 1419.33  5080.5 1419.81  5135.8 1421.97  5211.2 1427.86  5266.6 1429.88
  5287.2 1431.55  5293.5 1434.74  5298.6 1433.58  5318.0 1435.20  5377.1 1436.32
  5465.9 1439.80  5502.5 1439.71  5507.7 1441.42  5513.5 1440.36  5530.0 1441.79
#Mann=3,-1,0
  4696.0    0.05       0  4995.8    0.03       0  4999.8    0.05       0
Bank Sta=4995.8,4999.8
Exp/Cntr=0.3,0.1

Type RM Length L Ch R = 1,10106,525,525,525
BEGIN DESCRIPTION:
NORTH HELMS CREEK 20.0
END DESCRIPTION:
XS GIS Cut Line= 3
      2767946.37     10167701.60      2768125.53     10167222.70
      2768182.43     10166877.98
#Sta/Elev= 30
  4634.8 1434.41  4642.8 1434.71  4648.2 1433.08  4665.2 1435.36  4678.4 1434.96
  4686.6 1435.63  4697.2 1434.65  4703.4 1432.34  4708.7 1434.05  4728.3 1431.18
  4733.7 1432.13  4740.0 1430.23  4750.6 1428.80  4819.2 1422.35  4874.4 1420.50
  4879.8 1419.72  4929.7 1419.22  4953.5 1417.60  4984.9 1413.19  4994.2 1412.54
  4994.4 1409.54  4997.9 1409.54  4998.2 1412.54  5006.9 1412.79  5015.2 1415.55
  5045.5 1418.00  5050.8 1417.40  5131.0 1421.43  5235.5 1423.85  5495.5 1436.10
#Mann=3,-1,0
  4634.8    0.05       0  4994.2    0.05       0  4998.2    0.05       0
Bank Sta=4994.2,4998.2
Exp/Cntr=0.3,0.1

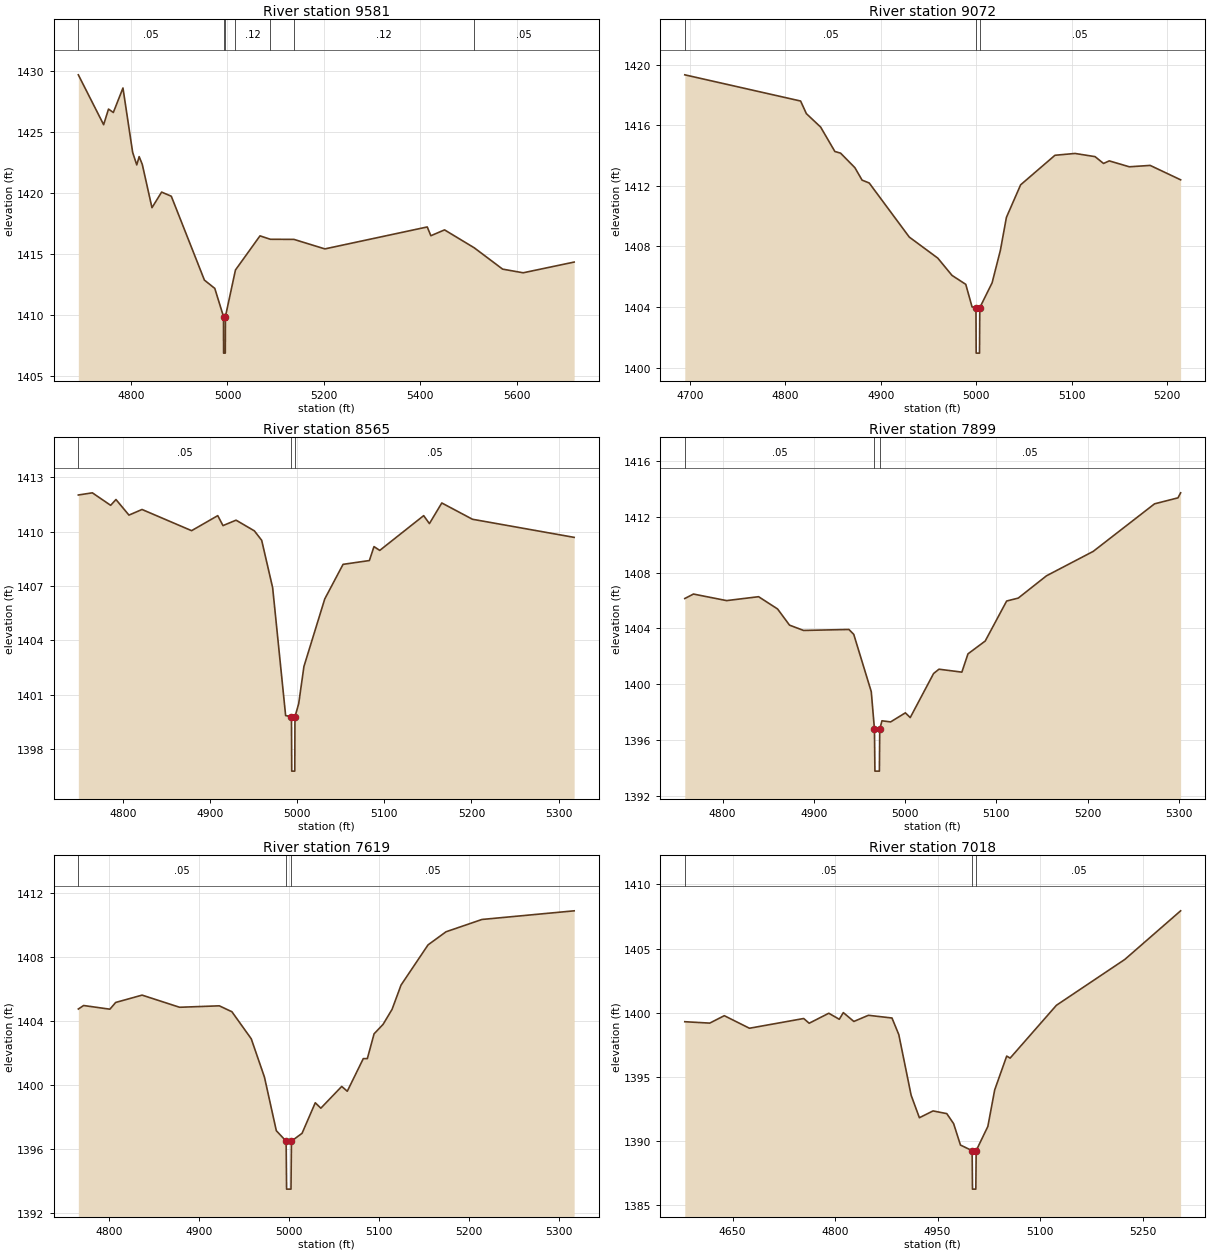
Type RM Length L Ch R = 1,9581,509,509,509
BEGIN DESCRIPTION:
NORTH HELMS CREEK 19.0
END DESCRIPTION:
XS GIS Cut Line= 3
      2767993.27     10167786.99      2768360.12     10167760.80
      2768853.92     10167321.50
#Sta/Elev= 30
  4690.6 1429.68  4743.1 1425.59  4753.2 1426.87  4763.2 1426.59  4783.2 1428.60
  4803.3 1423.32  4811.8 1422.29  4816.8 1422.97  4823.3 1422.33  4843.4 1418.78
  4863.4 1420.06  4883.5 1419.72  4952.2 1412.84  4973.7 1412.16  4991.8 1409.85
  4992.0 1406.85  4995.5 1406.85  4995.8 1409.85  5016.6 1413.67  5067.5 1416.47
  5088.9 1416.19  5138.0 1416.18  5202.1 1415.40  5414.5 1417.20  5422.0 1416.48
  5450.4 1416.96  5512.0 1415.49  5570.9 1413.74  5613.5 1413.44  5719.3 1414.32
#Mann=7,-1,0
  4690.6    0.05       0  4991.8    0.05       0  4995.8    0.05       0
  5016.6    0.12       0  5088.9    0.05       0  5138.0    0.12       0
  5512.0    0.05       0
Bank Sta=4991.8,4995.8
Exp/Cntr=0.3,0.1

Type RM Length L Ch R = 1,9072,507,507,507
BEGIN DESCRIPTION:
NORTH HELMS CREEK 18.0
END DESCRIPTION:
XS GIS Cut Line= 2
      2768391.79     10168197.23      2768822.13     10167905.87
#Sta/Elev= 30
  4694.6 1419.32  4816.0 1417.59  4822.0 1416.76  4837.0 1415.87  4851.9 1414.26
  4857.9 1414.15  4872.9 1413.19  4880.4 1412.37  4887.9 1412.18  4929.9 1408.61
  4959.8 1407.22  4974.7 1406.08  4989.1 1405.49  4995.7 1404.00  4999.8 1403.95
  5000.0 1400.95  5003.5 1400.95  5003.8 1403.95  5016.7 1405.59  5025.4 1407.74
  5031.7 1409.91  5046.6 1412.06  5082.6 1414.01  5103.6 1414.13  5124.6 1413.92
  5133.5 1413.47  5139.5 1413.64  5160.5 1413.25  5182.4 1413.34  5214.3 1412.39
#Mann=3,-1,0
  4694.6    0.05       0  4999.8    0.05       0  5003.8    0.05       0
Bank Sta=4999.8,5003.8
Exp/Cntr=0.3,0.1

Type RM Length L Ch R = 1,8565,666,666,666
BEGIN DESCRIPTION:
NORTH HELMS CREEK 17.0
END DESCRIPTION:
XS GIS Cut Line= 3
      2768848.91     10168597.43      2769036.00     10168320.75
      2769190.49     10168143.66
#Sta/Elev= 30
  4748.9 1412.03  4765.0 1412.15  4786.0 1411.46  4792.1 1411.78  4807.0 1410.92
  4822.0 1411.23  4878.9 1410.06  4908.9 1410.89  4914.9 1410.34  4929.9 1410.64
  4950.9 1410.05  4959.3 1409.53  4971.9 1406.91  4986.8 1399.85  4993.5 1399.78
  4993.8 1396.78  4997.3 1396.78  4997.5 1399.78  5001.8 1400.51  5007.8 1402.56
  5031.7 1406.29  5052.7 1408.20  5082.9 1408.41  5088.2 1409.18  5094.8 1408.97
  5145.2 1410.89  5151.8 1410.45  5166.0 1411.59  5201.2 1410.69  5317.9 1409.69
#Mann=3,-1,0
  4748.9    0.05       0  4993.5    0.05       0  4997.5    0.05       0
Bank Sta=4993.5,4997.5
Exp/Cntr=0.3,0.1

Type RM Length L Ch R = 1,7899,280,280,280
BEGIN DESCRIPTION:
NORTH HELMS CREEK 16.0
END DESCRIPTION:
XS GIS Cut Line= 3
      2769470.16     10168741.43      2769558.88     10168666.09
      2769700.94     10168263.30
#Sta/Elev= 30
  4758.5 1406.14  4768.0 1406.46  4804.3 1405.99  4839.4 1406.27  4860.2 1405.39
  4873.3 1404.23  4888.7 1403.85  4938.4 1403.92  4943.7 1403.57  4962.9 1399.46
  4966.4 1396.76  4966.9 1393.76  4971.8 1393.76  4972.2 1396.76  4974.6 1397.37
  4984.1 1397.29  5000.3 1397.94  5005.6 1397.60  5031.2 1400.76  5037.1 1401.07
  5062.2 1400.86  5068.9 1402.17  5087.8 1403.09  5111.3 1405.96  5124.0 1406.17
  5155.0 1407.77  5206.2 1409.52  5273.4 1412.93  5299.1 1413.36  5302.0 1413.72
#Mann=3,-1,0
  4758.5    0.05       0  4966.4    0.03       0  4972.2    0.05       0
Bank Sta=4966.4,4972.2
Exp/Cntr=0.3,0.1

Type RM Length L Ch R = 1,7619,601,601,601
BEGIN DESCRIPTION:
NORTH HELMS CREEK 15.0
END DESCRIPTION:
XS GIS Cut Line= 3
      2769716.31     10168851.60      2769903.02     10168593.12
      2769910.93     10168360.72
#Sta/Elev= 30
  4765.7 1404.75  4771.6 1404.97  4800.8 1404.74  4807.2 1405.16  4836.6 1405.62
  4878.3 1404.86  4922.5 1404.95  4936.5 1404.58  4958.0 1402.89  4972.7 1400.49
  4985.9 1397.14  4996.8 1396.49  4997.3 1393.49  5002.2 1393.49  5002.7 1396.49
  5014.5 1396.98  5029.2 1398.89  5035.4 1398.55  5058.6 1399.91  5064.8 1399.61
  5082.6 1401.65  5087.1 1401.65  5094.6 1403.20  5104.6 1403.79  5114.6 1404.73
  5124.6 1406.25  5154.6 1408.76  5174.6 1409.58  5214.6 1410.35  5317.1 1410.89
#Mann=3,-1,0
  4765.7    0.05       0  4996.8    0.05       0  5002.7    0.05       0
Bank Sta=4996.8,5002.7
Exp/Cntr=0.3,0.1

Type RM Length L Ch R = 1,7018,236,236,236
BEGIN DESCRIPTION:
NORTH HELMS CREEK 14.0
END DESCRIPTION:
XS GIS Cut Line= 3
      2770140.46     10169097.76      2770387.50     10168946.64
      2770418.74     10168511.76
#Sta/Elev= 30
  4580.1 1399.29  4616.6 1399.18  4637.9 1399.76  4674.7 1398.78  4754.1 1399.54
  4762.1 1399.17  4790.8 1399.95  4806.2 1399.48  4812.1 1400.00  4827.5 1399.31
  4848.8 1399.79  4883.3 1399.58  4893.3 1398.28  4911.3 1393.56  4923.4 1391.80
  4943.4 1392.33  4963.5 1392.12  4973.5 1391.34  4983.5 1389.67  5000.6 1389.23
  5001.1 1386.23  5006.0 1386.23  5006.5 1389.23  5023.6 1391.12  5033.6 1393.97
  5051.2 1396.61  5056.2 1396.45  5123.9 1400.57  5224.1 1404.15  5305.7 1407.94
#Mann=3,-1,0
  4580.1    0.05       0  5000.6    0.05       0  5006.5    0.05       0
Bank Sta=5000.6,5006.5
Exp/Cntr=0.3,0.1

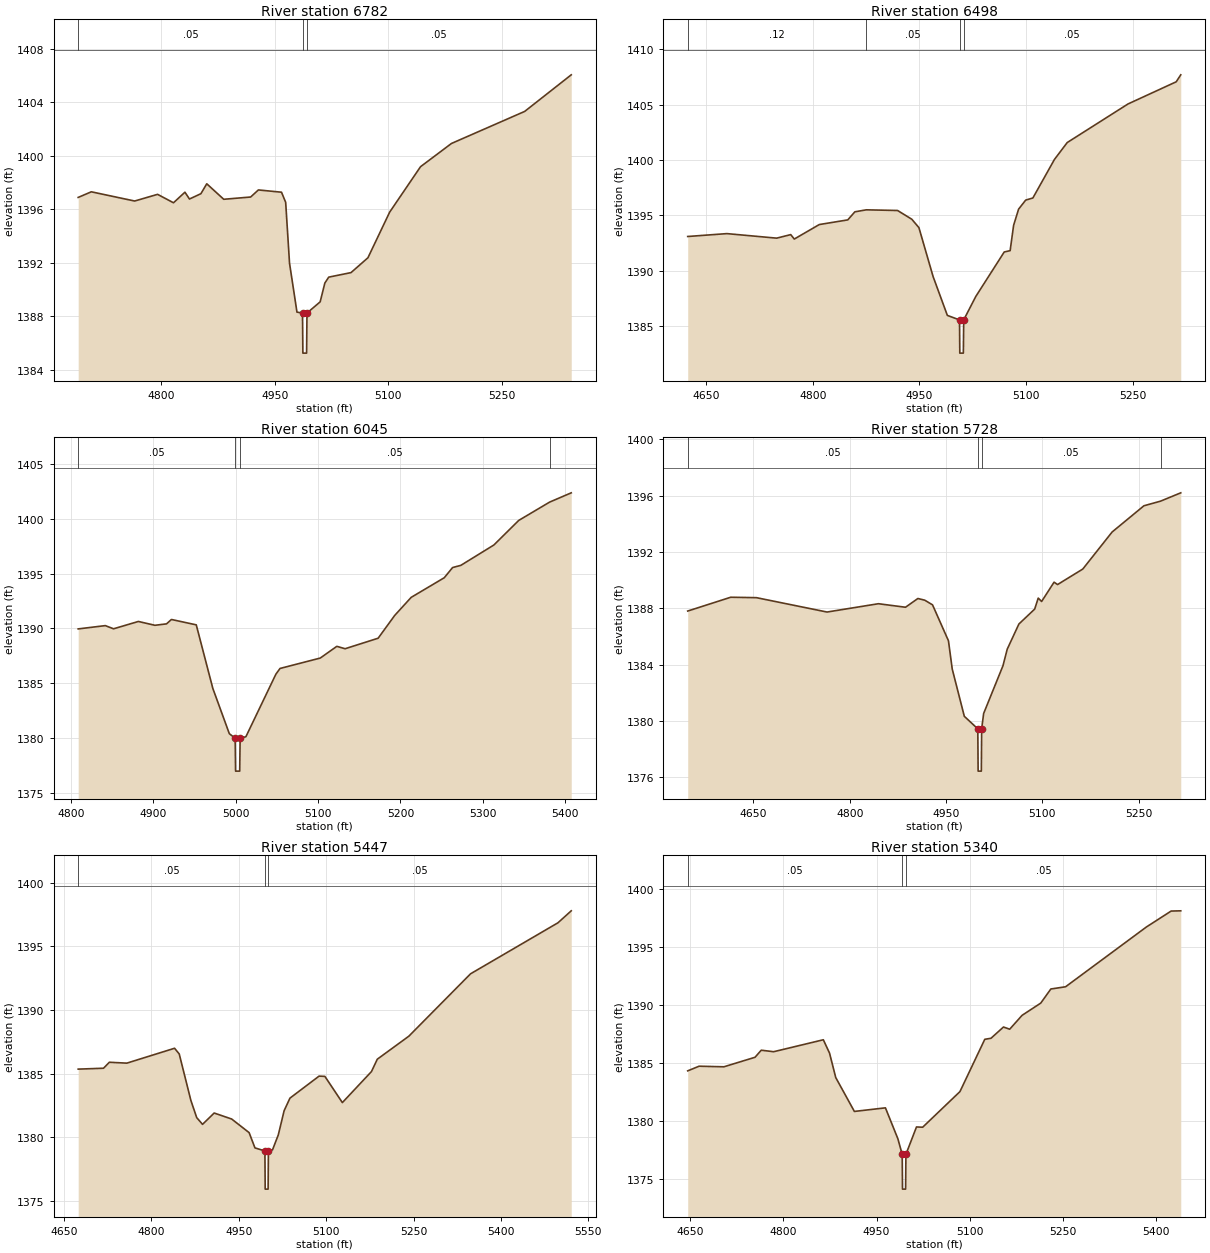
Type RM Length L Ch R = 1,6782,284,284,284
BEGIN DESCRIPTION:
NORTH HELMS CREEK 13.0
END DESCRIPTION:
XS GIS Cut Line= 3
      2770512.50     10169084.65      2770631.68     10168903.97
      2770548.97     10168477.97
#Sta/Elev= 30
  4690.8 1396.89  4708.1 1397.31  4765.3 1396.62  4795.5 1397.12  4816.5 1396.49
  4831.6 1397.28  4837.6 1396.77  4852.7 1397.17  4860.4 1397.91  4882.8 1396.75
  4918.3 1396.92  4928.5 1397.45  4959.0 1397.28  4964.5 1396.52  4969.6 1391.96
  4979.4 1388.30  4986.7 1388.23  4987.2 1385.23  4992.1 1385.23  4992.6 1388.23
  5010.0 1389.07  5016.2 1390.48  5021.3 1390.92  5050.7 1391.26  5073.0 1392.37
  5101.7 1395.79  5142.4 1399.19  5183.2 1400.93  5279.8 1403.33  5341.2 1406.07
#Mann=3,-1,0
  4690.8    0.05       0  4986.7    0.05       0  4992.6    0.05       0
Bank Sta=4986.7,4992.6
Exp/Cntr=0.3,0.1

Type RM Length L Ch R = 1,6498,453,453,453
BEGIN DESCRIPTION:
NORTH HELMS CREEK 12.0
END DESCRIPTION:
XS GIS Cut Line= 3
      2770895.31     10169108.14      2770881.39     10168657.64
      2770851.21     10168416.74
#Sta/Elev= 30
  4624.0 1393.08  4679.1 1393.34  4749.1 1392.93  4768.9 1393.25  4773.9 1392.85
  4809.1 1394.16  4849.1 1394.58  4859.1 1395.31  4875.2 1395.49  4919.2 1395.43
  4939.2 1394.64  4949.2 1393.88  4969.2 1389.45  4989.2 1385.95  5006.3 1385.54
  5006.7 1382.54  5011.7 1382.54  5012.2 1385.54  5029.2 1387.66  5069.2 1391.68
  5077.5 1391.80  5082.4 1394.09  5089.4 1395.55  5099.4 1396.37  5109.5 1396.56
  5139.8 1400.04  5157.8 1401.57  5243.4 1405.06  5311.1 1407.06  5317.5 1407.69
#Mann=4,-1,0
  4624.0    0.12       0  4875.2    0.05       0  5006.3    0.05       0
  5012.2    0.05       0
Bank Sta=5006.3,5012.2
Exp/Cntr=0.3,0.1

Type RM Length L Ch R = 1,6045,317,317,317
BEGIN DESCRIPTION:
Mapping XS b1871c9c
END DESCRIPTION:
XS GIS Cut Line= 2
      2771288.54     10169115.93      2771244.27     10168519.57
#Sta/Elev= 30
  4809.1 1389.96  4842.0 1390.26  4852.0 1389.97  4882.1 1390.64  4902.2 1390.29
  4916.2 1390.42  4922.2 1390.82  4952.3 1390.33  4972.4 1384.53  4992.4 1380.40
  4999.5 1379.98  5000.0 1376.98  5005.0 1376.98  5005.5 1379.98  5012.5 1380.12
  5048.9 1385.83  5053.9 1386.35  5102.7 1387.30  5122.8 1388.37  5132.8 1388.15
  5172.9 1389.11  5193.0 1391.19  5213.0 1392.84  5253.1 1394.63  5263.2 1395.56
  5273.2 1395.76  5313.3 1397.62  5343.4 1399.86  5380.8 1401.53  5407.1 1402.38
#Mann=4,-1,0
  4809.1    0.05       0  4999.5    0.05       0  5005.5    0.05       0
  5380.8    0.12       0
Bank Sta=4999.5,5005.5
Exp/Cntr=0.3,0.1

Type RM Length L Ch R = 1,5728,281,281,281
BEGIN DESCRIPTION:
Mapping XS 26d19b55
END DESCRIPTION:
XS GIS Cut Line= 3
      2771588.02     10169220.11      2771585.41     10168884.14
      2771431.76     10168480.47
#Sta/Elev= 30
  4547.7 1387.80  4614.7 1388.78  4654.7 1388.75  4764.7 1387.73  4844.7 1388.32
  4886.9 1388.07  4906.2 1388.69  4916.9 1388.57  4929.0 1388.24  4953.8 1385.69
  4959.7 1383.68  4978.5 1380.33  4999.5 1379.44  5000.0 1376.44  5005.0 1376.44
  5005.5 1379.44  5008.6 1380.53  5038.7 1383.92  5045.3 1385.09  5063.5 1386.88
  5088.1 1387.94  5093.6 1388.72  5098.9 1388.48  5118.3 1389.85  5123.7 1389.68
  5163.0 1390.78  5208.7 1393.41  5258.2 1395.27  5284.2 1395.60  5315.6 1396.19
#Mann=4,-1,0
  4547.7    0.05       0  4999.5    0.05       0  5005.5    0.05       0
  5284.2    0.12       0
Bank Sta=4999.5,5005.5
Exp/Cntr=0.3,0.1

Type RM Length L Ch R = 1,5447,107,107,107
BEGIN DESCRIPTION:
NORTH HELMS CREEK 11.0
END DESCRIPTION:
XS GIS Cut Line= 3
      2771767.70     10168946.61      2771778.12     10168378.93
      2771788.54     10168100.30
#Sta/Elev= 30
  4674.2 1385.36  4717.7 1385.43  4727.7 1385.90  4757.7 1385.83  4839.7 1387.00
  4847.7 1386.55  4867.7 1382.90  4877.7 1381.55  4887.7 1381.02  4907.7 1381.91
  4937.7 1381.44  4967.7 1380.37  4977.7 1379.17  4994.8 1378.93  4995.3 1375.93
  5000.3 1375.93  5000.8 1378.93  5007.8 1379.01  5017.8 1380.19  5027.8 1382.09
  5037.8 1383.08  5087.8 1384.81  5097.8 1384.79  5127.8 1382.73  5177.8 1385.17
  5187.8 1386.14  5242.0 1387.95  5347.9 1392.85  5498.0 1396.86  5520.8 1397.80
#Mann=3,-1,0
  4674.2    0.05       0  4994.8    0.03       0  5000.8    0.05       0
Bank Sta=4994.8,5000.8
Exp/Cntr=0.3,0.1

Type RM Length L Ch R = 1,5340,190,190,190
BEGIN DESCRIPTION:
NORTH HELMS CREEK 10.0
END DESCRIPTION:
XS GIS Cut Line= 3
      2771866.66     10168941.44      2771879.68     10168355.49
      2771874.49     10168147.65
#Sta/Elev= 30
  4645.9 1384.36  4664.2 1384.76  4704.2 1384.71  4754.3 1385.53  4764.3 1386.14
  4784.3 1386.01  4864.3 1387.04  4874.3 1385.89  4884.3 1383.78  4914.3 1380.86
  4964.3 1381.17  4984.3 1378.51  4991.3 1377.16  4991.8 1374.16  4996.8 1374.16
  4997.3 1377.16  5014.3 1379.52  5024.3 1379.50  5084.3 1382.57  5124.3 1387.08
  5134.3 1387.17  5154.4 1388.14  5164.4 1387.95  5184.4 1389.15  5214.4 1390.20
  5230.7 1391.42  5254.4 1391.61  5384.4 1396.76  5424.4 1398.14  5439.9 1398.16
#Mann=3,-1,0
  4645.9    0.05       0  4991.3    0.05       0  4997.3    0.05       0
Bank Sta=4991.3,4997.3
Exp/Cntr=0.3,0.1

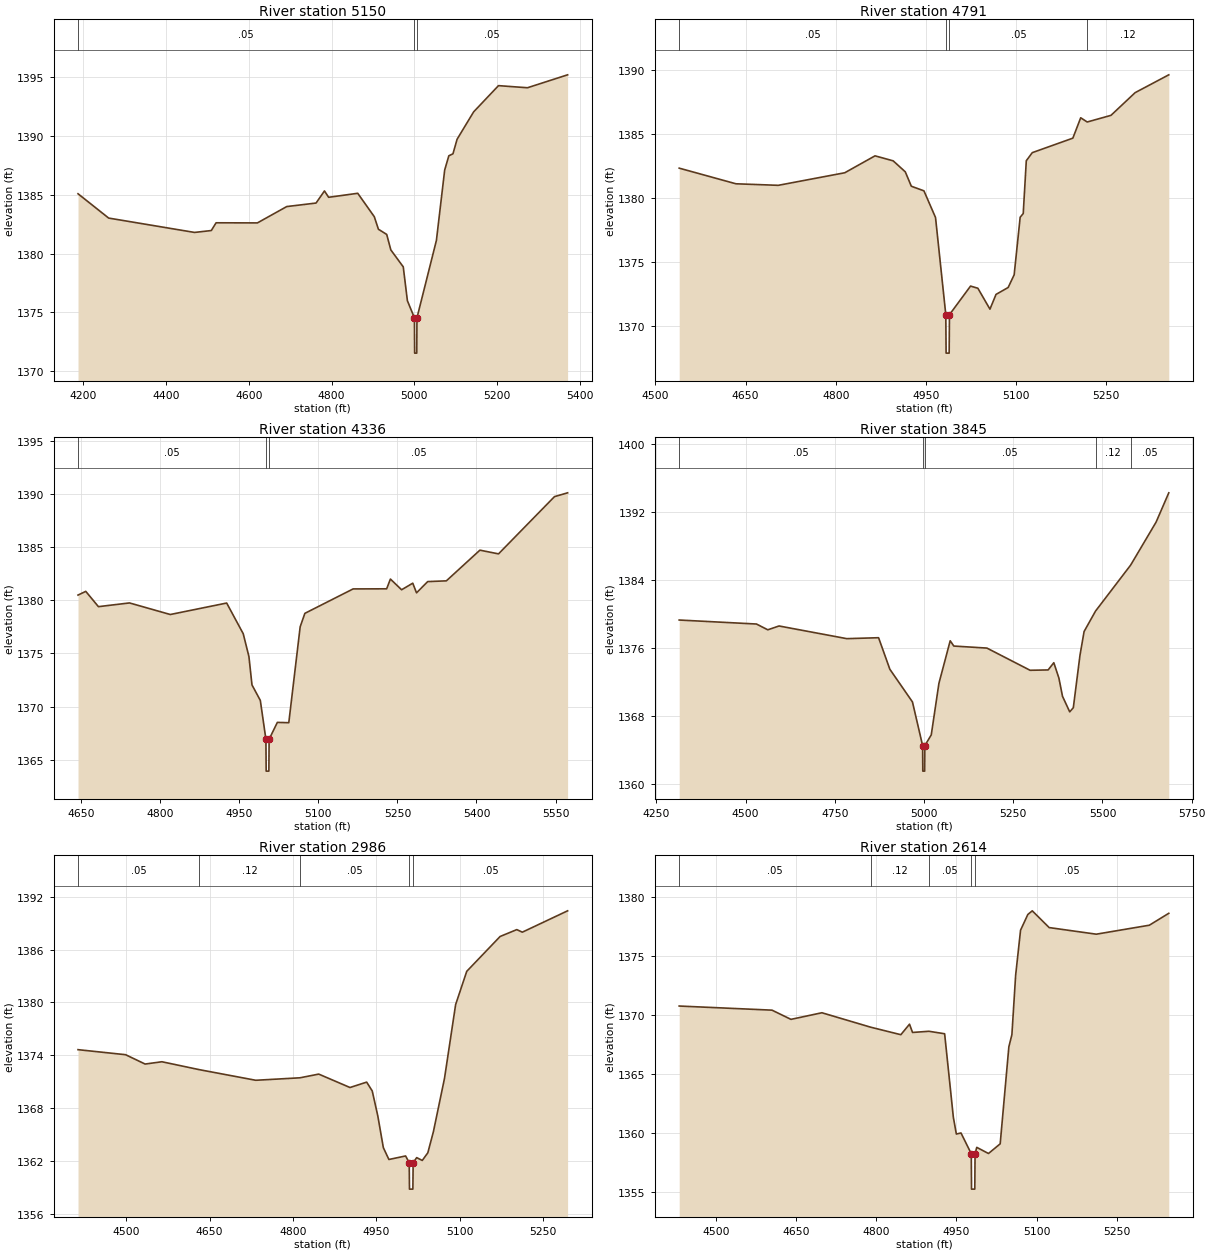
Type RM Length L Ch R = 1,5150,359,359,359
BEGIN DESCRIPTION:
NORTH HELMS CREEK 9.0
END DESCRIPTION:
XS GIS Cut Line= 3
      2772132.29     10169311.24      2772033.33     10168686.22
      2772043.71     10168136.12
#Sta/Elev= 30
  4187.3 1385.10  4261.4 1383.03  4468.9 1381.81  4509.4 1381.97  4520.9 1382.63
  4620.8 1382.62  4691.6 1384.01  4762.5 1384.31  4782.8 1385.34  4792.9 1384.80
  4863.2 1385.14  4903.2 1383.15  4913.2 1382.08  4933.2 1381.64  4943.2 1380.32
  4973.2 1378.88  4983.2 1376.00  5000.2 1374.54  5000.7 1371.54  5005.8 1371.54
  5006.3 1374.54  5053.3 1381.13  5073.3 1387.12  5083.3 1388.33  5093.3 1388.50
  5103.3 1389.74  5143.3 1392.07  5203.3 1394.30  5273.3 1394.12  5370.3 1395.22
#Mann=3,-1,0
  4187.3    0.05       0  5000.2    0.05       0  5006.3    0.05       0
Bank Sta=5000.2,5006.3
Exp/Cntr=0.3,0.1

Type RM Length L Ch R = 1,4791,455,455,455
BEGIN DESCRIPTION:
Mapping XS 691cbd3c
END DESCRIPTION:
XS GIS Cut Line= 2
      2772408.33     10169076.83      2772312.04     10168267.54
#Sta/Elev= 30
  4539.5 1382.35  4633.9 1381.13  4704.4 1381.01  4815.1 1381.99  4865.5 1383.31
  4895.7 1382.92  4915.9 1382.06  4925.9 1380.94  4946.9 1380.58  4966.2 1378.50
  4983.3 1370.92  4983.8 1367.92  4988.9 1367.92  4989.4 1370.92  5024.5 1373.15
  5036.7 1372.98  5056.8 1371.35  5066.9 1372.50  5087.1 1373.04  5097.1 1374.03
  5107.1 1378.52  5112.2 1378.81  5117.3 1382.93  5127.3 1383.56  5194.8 1384.69
  5207.9 1386.28  5218.7 1385.95  5258.3 1386.47  5298.5 1388.24  5354.5 1389.63
#Mann=4,-1,0
  4539.5    0.05       0  4983.3    0.05       0  4989.4    0.05       0
  5218.7    0.12       0
Bank Sta=4983.3,4989.4
Exp/Cntr=0.3,0.1

Type RM Length L Ch R = 1,4336,491,491,491
BEGIN DESCRIPTION:
NORTH HELMS CREEK 8.0
END DESCRIPTION:
XS GIS Cut Line= 3
      2772905.68     10168853.10      2772741.62     10168451.68
      2772390.42     10168103.21
#Sta/Elev= 30
  4644.4 1380.50  4659.1 1380.85  4683.1 1379.41  4742.0 1379.76  4819.4 1378.67
  4926.3 1379.75  4957.7 1376.86  4968.5 1374.71  4974.3 1372.04  4990.1 1370.58
  5000.7 1366.92  5001.2 1363.92  5006.3 1363.92  5006.8 1366.92  5022.4 1368.51
  5044.1 1368.48  5065.7 1377.52  5074.6 1378.78  5166.1 1381.08  5229.7 1381.09
  5236.8 1382.01  5258.0 1381.00  5279.2 1381.62  5286.3 1380.71  5307.5 1381.77
  5342.9 1381.84  5406.5 1384.73  5441.8 1384.38  5547.9 1389.77  5572.8 1390.13
#Mann=3,-1,0
  4644.4    0.05       0  5000.7    0.05       0  5006.8    0.05       0
Bank Sta=5000.7,5006.8
Exp/Cntr=0.3,0.1

Type RM Length L Ch R = 1,3845,859,859,859
BEGIN DESCRIPTION:
NORTH HELMS CREEK 7.0
END DESCRIPTION:
XS GIS Cut Line= 3
      2773002.09     10169173.17      2773259.89     10168399.76
      2773332.78     10167847.89
#Sta/Elev= 30
  4314.0 1379.32  4530.5 1378.85  4562.2 1378.17  4593.8 1378.62  4783.5 1377.13
  4872.7 1377.24  4904.3 1373.53  4967.6 1369.69  4996.1 1364.55  4996.6 1361.55
  5001.8 1361.55  5002.3 1364.55  5020.3 1365.81  5041.8 1371.88  5073.4 1376.88
  5083.5 1376.26  5176.3 1376.02  5297.3 1373.41  5347.8 1373.45  5363.7 1374.30
  5378.0 1372.49  5388.1 1370.35  5408.3 1368.52  5418.4 1369.01  5437.1 1375.19
  5448.6 1377.97  5480.6 1380.37  5579.2 1385.79  5650.4 1390.84  5685.9 1394.28
#Mann=5,-1,0
  4314.0    0.05       0  4996.1    0.05       0  5002.3    0.05       0
  5480.6    0.12       0  5579.2    0.05       0
Bank Sta=4996.1,5002.3
Exp/Cntr=0.3,0.1

Type RM Length L Ch R = 1,2986,372,372,372
BEGIN DESCRIPTION:
NORTH HELMS CREEK 6.0
END DESCRIPTION:
XS GIS Cut Line= 3
      2773747.29     10168838.96      2773955.48     10168459.31
      2773963.02     10168011.76
#Sta/Elev= 30
  4413.3 1374.65  4498.8 1374.08  4534.0 1373.02  4564.2 1373.28  4631.0 1372.39
  4733.0 1371.18  4812.4 1371.46  4846.3 1371.88  4902.5 1370.36  4932.5 1370.97
  4942.5 1369.97  4952.5 1367.15  4962.5 1363.54  4972.5 1362.20  5002.5 1362.60
  5009.0 1361.84  5009.5 1358.84  5015.6 1358.84  5016.1 1361.84  5022.5 1362.41
  5032.5 1362.09  5042.5 1362.96  5052.5 1365.34  5072.5 1371.40  5092.5 1379.76
  5112.5 1383.53  5172.5 1387.48  5202.5 1388.26  5212.5 1387.97  5293.9 1390.39
#Mann=5,-1,0
  4413.3    0.05       0  4631.0    0.12       0  4812.4    0.05       0
  5009.0    0.05       0  5016.1    0.05       0
Bank Sta=5009,5016.1
Exp/Cntr=0.3,0.1

Type RM Length L Ch R = 1,2614,406,406,406
BEGIN DESCRIPTION:
NORTH HELMS CREEK 5.0
END DESCRIPTION:
XS GIS Cut Line= 3
      2774046.36     10168897.14      2774374.48     10168287.79
      2774338.15     10168067.24
#Sta/Elev= 30
  4431.5 1370.80  4605.1 1370.45  4640.5 1369.67  4698.4 1370.23  4789.3 1369.01
  4846.0 1368.37  4862.2 1369.26  4867.9 1368.56  4898.4 1368.66  4927.9 1368.45
  4944.2 1361.37  4949.8 1359.95  4958.5 1360.04  4977.7 1358.28  4978.2 1355.28
  4984.3 1355.28  4984.8 1358.28  4988.0 1358.82  5009.9 1358.30  5031.8 1359.12
  5048.0 1367.34  5053.7 1368.38  5060.7 1373.41  5069.9 1377.23  5083.5 1378.56
  5091.8 1378.87  5123.4 1377.45  5211.5 1376.89  5310.7 1377.65  5347.1 1378.66
#Mann=5,-1,0
  4431.5    0.05       0  4789.3    0.12       0  4898.4    0.05       0
  4977.7    0.03       0  4984.8    0.05       0
Bank Sta=4977.7,4984.8
Exp/Cntr=0.3,0.1

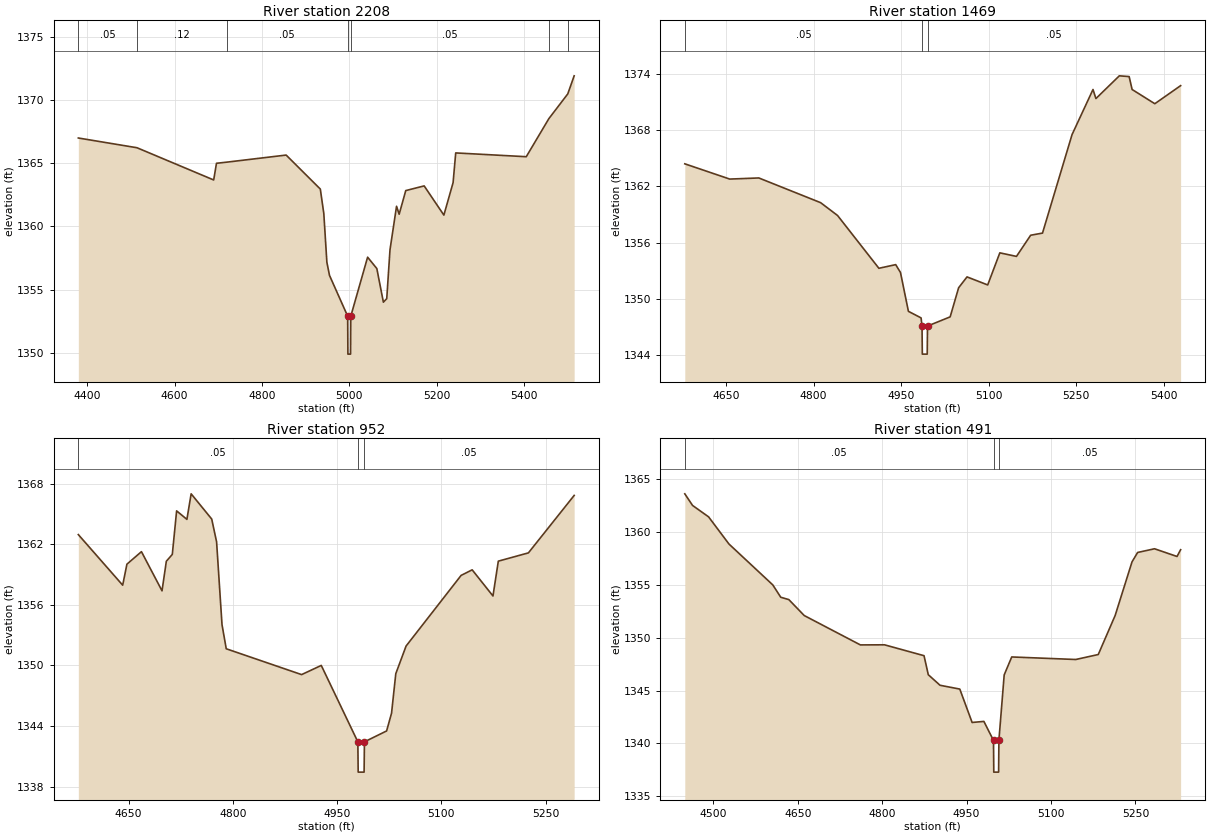
Type RM Length L Ch R = 1,2208,739,739,739
BEGIN DESCRIPTION:
NORTH HELMS CREEK 4.0
END DESCRIPTION:
XS GIS Cut Line= 3
      2774345.82     10169061.24      2774838.02     10168319.04
      2775064.31     10168228.00
#Sta/Elev= 30
  4379.9 1367.00  4514.1 1366.23  4689.6 1363.68  4696.0 1365.00  4719.7 1365.09
  4855.4 1365.65  4933.6 1362.96  4941.6 1361.02  4948.6 1357.17  4954.6 1356.13
  4996.2 1352.90  4996.7 1349.90  5002.8 1349.90  5003.3 1352.90  5041.8 1357.57
  5062.9 1356.67  5077.9 1354.01  5085.6 1354.29  5093.0 1358.15  5108.0 1361.60
  5114.0 1360.97  5129.1 1362.84  5171.2 1363.21  5216.3 1360.90  5237.4 1363.47
  5243.4 1365.82  5404.8 1365.52  5456.5 1368.53  5499.8 1370.49  5514.4 1371.92
#Mann=7,-1,0
  4379.9    0.05       0  4514.1    0.12       0  4719.7    0.05       0
  4996.2    0.05       0  5003.3    0.05       0  5456.5    0.12       0
  5499.8    0.05       0
Bank Sta=4996.2,5003.3
Exp/Cntr=0.3,0.1

Type RM Length L Ch R = 1,1469,517,517,517
BEGIN DESCRIPTION:
NORTH HELMS CREEK 3.0
END DESCRIPTION:
XS GIS Cut Line= 3
      2775580.19     10169056.00      2775231.25     10168605.49
      2775186.98     10168329.46
#Sta/Elev= 30
  4579.3 1364.41  4656.3 1362.78  4706.1 1362.90  4812.0 1360.26  4841.0 1358.89
  4911.8 1353.25  4940.6 1353.64  4948.8 1352.80  4962.4 1348.65  4984.1 1347.95
  4985.7 1347.08  4986.2 1344.08  4994.6 1344.08  4995.1 1347.08  5033.9 1348.06
  5048.4 1351.17  5062.8 1352.33  5098.2 1351.47  5119.0 1354.90  5147.5 1354.52
  5171.8 1356.78  5192.1 1357.01  5242.7 1367.53  5278.6 1372.35  5283.6 1371.38
  5323.7 1373.81  5340.5 1373.73  5345.6 1372.35  5384.5 1370.83  5428.7 1372.76
#Mann=3,-1,0
  4579.3    0.05       0  4985.7    0.03       0  4995.1    0.05       0
Bank Sta=4985.7,4995.1
Exp/Cntr=0.3,0.1

Type RM Length L Ch R = 1,952,461,461,461
BEGIN DESCRIPTION:
NORTH HELMS CREEK 2.0
END DESCRIPTION:
XS GIS Cut Line= 3
      2775840.60     10168675.78      2775558.67     10168275.36
      2775364.02     10168165.37
#Sta/Elev= 30
  4577.7 1362.96  4641.5 1357.95  4647.6 1360.03  4668.5 1361.27  4698.1 1357.39
  4704.3 1360.32  4712.9 1361.00  4719.1 1365.31  4733.9 1364.47  4740.0 1367.00
  4769.6 1364.50  4776.6 1362.24  4784.4 1354.04  4790.5 1351.65  4898.9 1349.09
  4927.2 1350.00  4979.8 1342.43  4980.3 1339.43  4988.8 1339.43  4989.3 1342.43
  5021.2 1343.51  5028.3 1345.27  5034.4 1349.18  5049.2 1351.92  5128.4 1358.92
  5144.3 1359.47  5174.2 1356.88  5181.9 1360.33  5225.2 1361.15  5291.0 1366.84
#Mann=3,-1,0
  4577.7    0.05       0  4979.8    0.05       0  4989.3    0.05       0
Bank Sta=4979.8,4989.3
Exp/Cntr=0.3,0.1

Type RM Length L Ch R = 1,491,0,0,0
BEGIN DESCRIPTION:
NORTH HELMS CREEK 1.0
END DESCRIPTION:
XS GIS Cut Line= 3
      2776305.71     10168453.14      2775882.29     10167962.26
      2775649.27     10167959.68
#Sta/Elev= 30
  4449.1 1363.62  4462.9 1362.52  4491.4 1361.44  4527.6 1358.87  4605.5 1355.00
  4619.7 1353.83  4634.0 1353.61  4661.4 1352.10  4761.2 1349.32  4804.0 1349.33
  4874.3 1348.30  4881.9 1346.50  4902.8 1345.50  4937.9 1345.14  4959.8 1341.98
  4980.7 1342.08  4997.8 1340.28  4998.3 1337.28  5006.9 1337.28  5007.4 1340.28
  5016.8 1346.48  5030.2 1348.18  5144.0 1347.94  5184.0 1348.41  5214.0 1352.10
  5244.0 1357.18  5254.0 1358.07  5284.0 1358.42  5324.0 1357.69  5330.4 1358.33
#Mann=3,-1,0
  4449.1    0.05       0  4997.8    0.03       0  5007.4    0.05       0
Bank Sta=4997.8,5007.4
Exp/Cntr=0.3,0.1

Chan Stop Cuts=-1