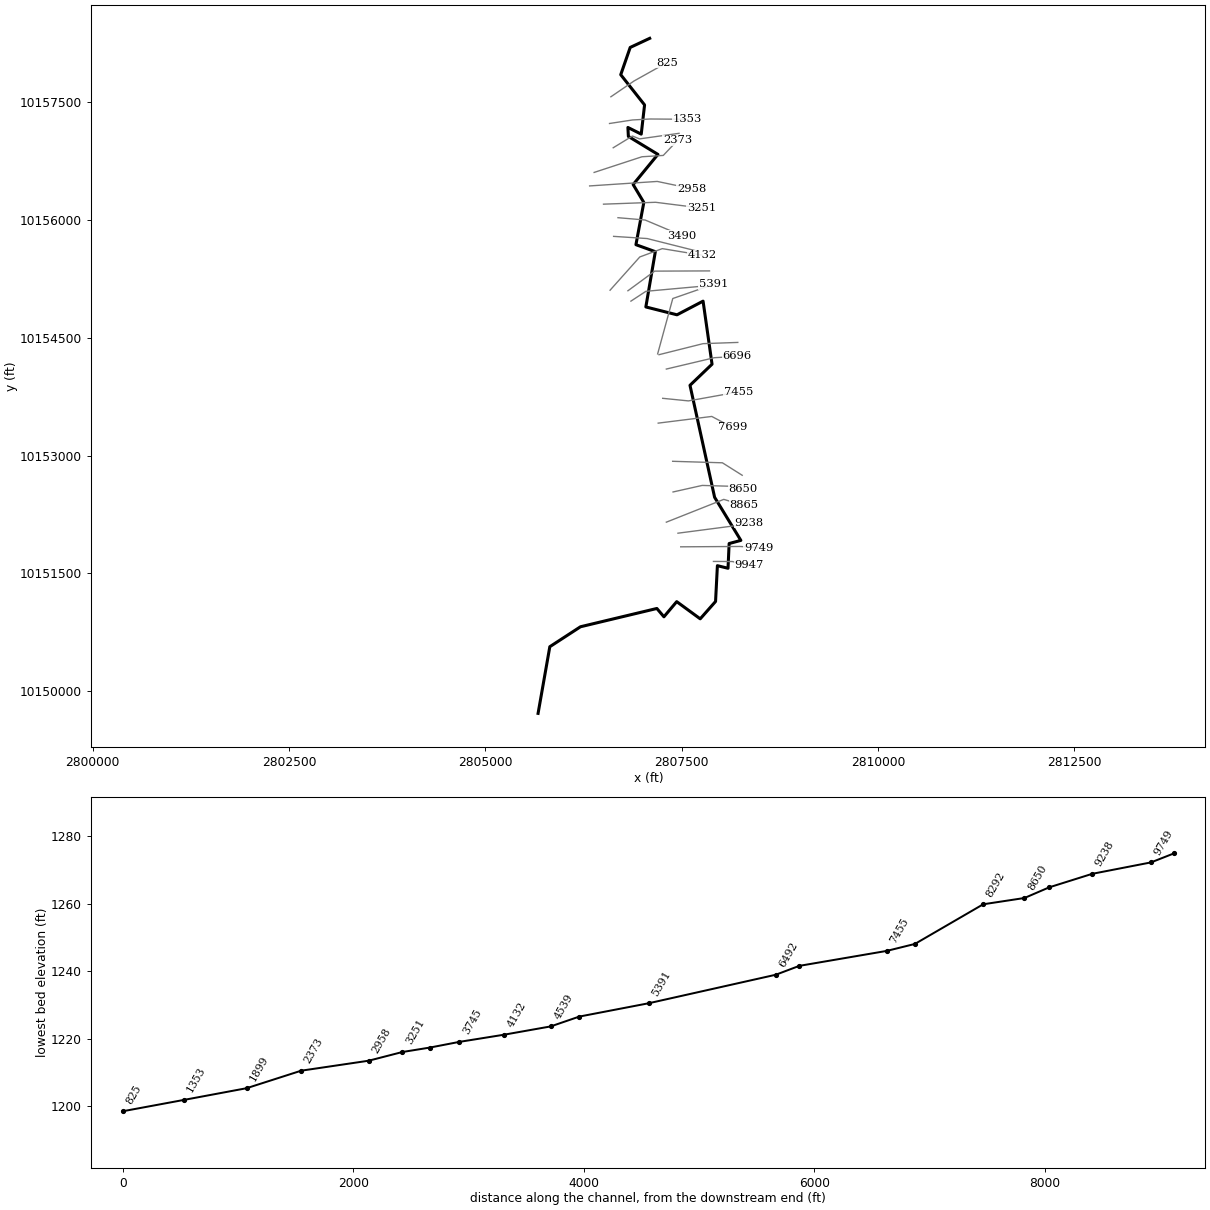
--- SANDY 09.prj (project) ---

Proj Title=SANDY 09 Base Level Engineering
Current Plan=p01
Default Exp/Contr=0.3,0.1
English Units
Geom File=g01
Flow File=f01
Plan File=p01
BEGIN DESCRIPTION:
SANDY 09
END DESCRIPTION:

--- SANDY 09.p01 (plan) ---

Plan Title=Multiple Run
Short Identifier=Multiple
Geom File=g01
Flow File=f01
Subcritical Flow
K Sum by GR= 0
Std Step Tol= 0.01
Critical Tol= 0.01
Num of Std Step Trials= 20
Max Error Tol= 0.3
Flow Tol Ratio= 0.001
Split Flow NTrial= 30
Split Flow Tol= 0.02
Split Flow Ratio= 0.02
Log Output Level= 0
Friction Slope Method= 1
Unsteady Friction Slope Method= 2
Unsteady Bridges Friction Slope Method= 1
Parabolic Critical Depth
Global Vel Dist=  1 , 1 , 1
Global Log Level= 0
CheckData=True
Encroach Param= -1, 0, 0, 0
BEGIN DESCRIPTION:
Multiple Run
END DESCRIPTION:

--- SANDY 09.f01 (steady flow) ---

Flow Title=Multiple
Number of Profiles=7
Profile Names=10-year,25-year,50-year,1pct_min,100-year,1pct_plu,500-year
River Rch & RM= SANDY 09,Reach-1,9947
      69     131     204     106     319     962     839
River Rch & RM= SANDY 09,Reach-1,4787
      85     169     268     141     425    1283    1144
Boundary for River Rch & Prof#=SANDY 09,Reach-1,1
Up Type=0
Dn Type=3
Dn Slope=0.005
Boundary for River Rch & Prof#=SANDY 09,Reach-1,2
Up Type=0
Dn Type=3
Dn Slope=0.005
Boundary for River Rch & Prof#=SANDY 09,Reach-1,3
Up Type=0
Dn Type=3
Dn Slope=0.005
Boundary for River Rch & Prof#=SANDY 09,Reach-1,4
Up Type=0
Dn Type=3
Dn Slope=0.005
Boundary for River Rch & Prof#=SANDY 09,Reach-1,5
Up Type=0
Dn Type=3
Dn Slope=0.005
Boundary for River Rch & Prof#=SANDY 09,Reach-1,6
Up Type=0
Dn Type=3
Dn Slope=0.005
Boundary for River Rch & Prof#=SANDY 09,Reach-1,7
Up Type=0
Dn Type=3
Dn Slope=0.005

--- SANDY 09.g01 (geometry) ---

Geom Title=Existing Conditions

River Reach=SANDY 09,Reach-1
Reach XY= 30
      2805672.25     10149718.00      2805821.75     10150567.00
      2806212.25     10150821.00      2807185.00     10151054.00
      2807275.00     10150948.00      2807437.75     10151141.00
      2807737.25     10150922.00      2807932.50     10151143.00
      2807956.00     10151599.00      2808091.25     10151566.00
      2808105.50     10151881.00      2808254.75     10151921.00
      2807920.50     10152470.00      2807607.00     10153896.00
      2807887.75     10154165.00      2807773.50     10154968.00
      2807441.50     10154794.00      2807044.75     10154894.00
      2807165.50     10155598.00      2806918.50     10155687.00
      2807019.00     10156225.00      2806883.00     10156453.00
      2807198.50     10156837.00      2806822.25     10157066.00
      2806816.25     10157180.00      2806986.00     10157095.00
      2807028.50     10157467.00      2806725.00     10157852.00
      2806845.50     10158199.00      2807093.75     10158315.00

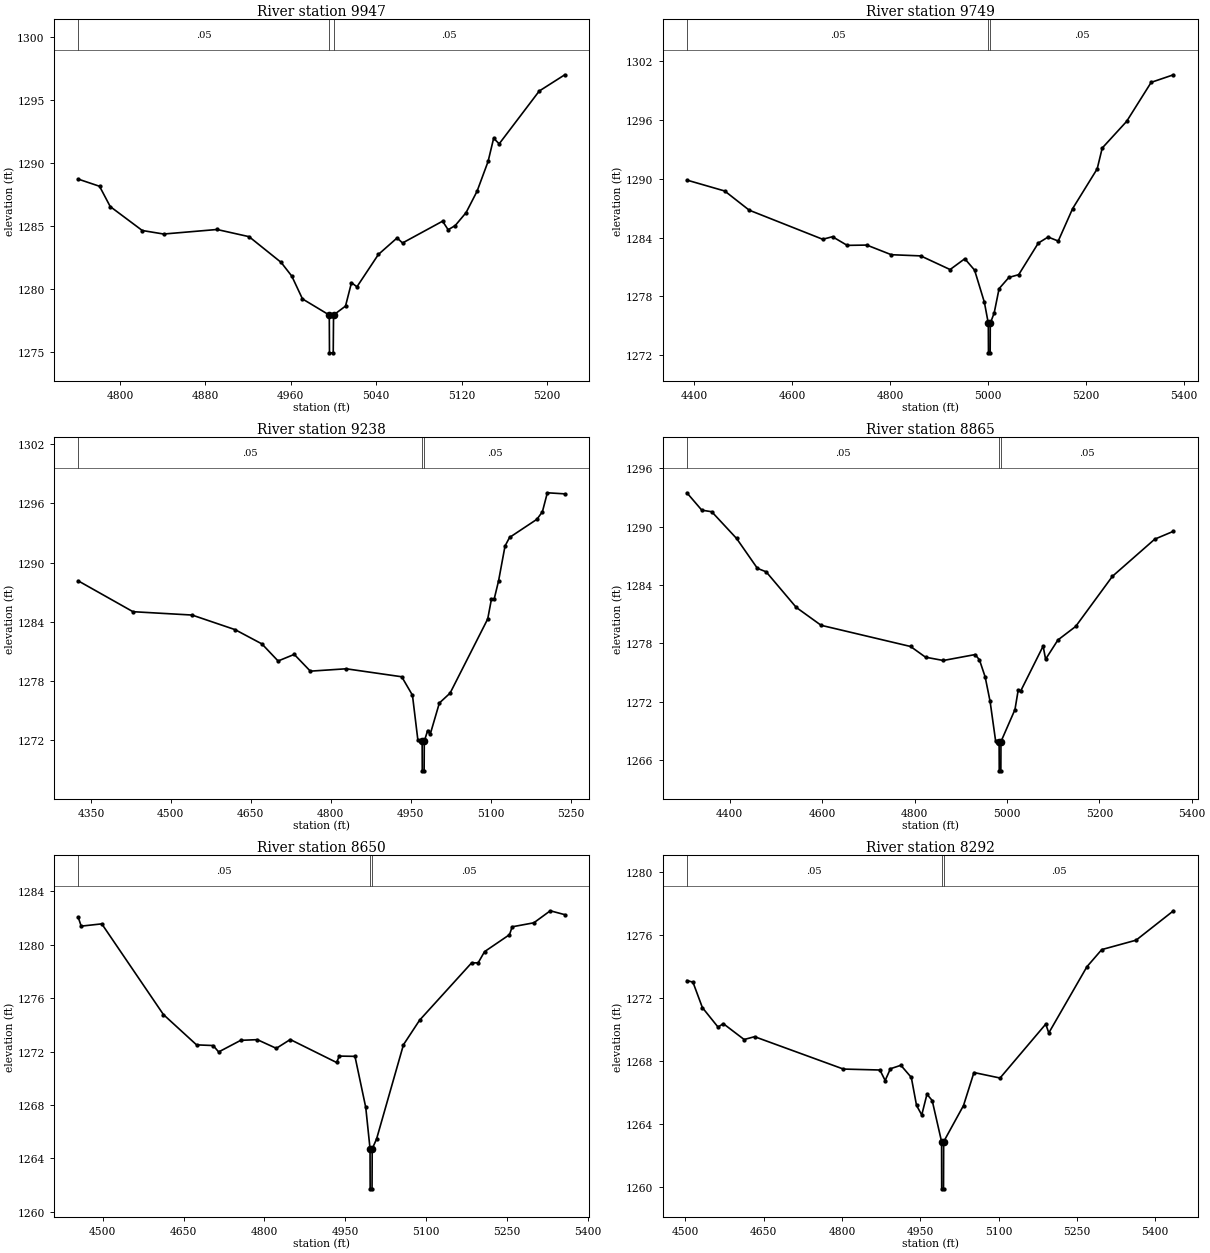
Type RM Length L Ch R = 1,9947,198,198,198
BEGIN DESCRIPTION:
SANDY 09 16.0
END DESCRIPTION:
XS GIS Cut Line= 3
      2807905.65     10151653.11      2808144.75     10151652.00
      2808355.66     10151603.12
#Sta/Elev= 30
  4760.9 1288.72  4780.9 1288.15  4790.9 1286.54  4820.9 1284.64  4840.9 1284.36
  4890.9 1284.72  4920.9 1284.15  4950.9 1282.11  4960.9 1281.02  4970.9 1279.21
  4996.0 1277.93  4996.2 1274.93  4999.7 1274.93  5000.0 1277.93  5011.2 1278.64
  5016.8 1280.50  5021.9 1280.17  5042.0 1282.74  5059.5 1284.05  5064.6 1283.65
  5102.1 1285.38  5107.3 1284.70  5113.9 1285.03  5124.1 1286.06  5134.4 1287.76
  5144.7 1290.12  5149.9 1291.96  5155.1 1291.52  5192.6 1295.71  5216.5 1297.00
#Mann=3,-1,0
  4760.9    0.05       0  4996.0    0.05       0  5000.0    0.05       0
Bank Sta=4996,5000
Exp/Cntr=0.3,0.1

Type RM Length L Ch R = 1,9749,511,511,511
BEGIN DESCRIPTION:
SANDY 09 15.0
END DESCRIPTION:
XS GIS Cut Line= 3
      2807488.48     10151839.13      2808242.06     10151843.69
      2808481.10     10151828.74
#Sta/Elev= 30
  4385.3 1289.84  4462.5 1288.73  4512.5 1286.78  4662.5 1283.82  4682.5 1284.08
  4712.5 1283.20  4752.5 1283.23  4802.5 1282.25  4862.5 1282.13  4922.5 1280.74
  4952.5 1281.84  4972.5 1280.68  4992.5 1277.41  5000.5 1275.27  5000.8 1272.27
  5004.3 1272.27  5004.5 1275.27  5012.5 1276.33  5022.5 1278.80  5042.5 1279.94
  5062.5 1280.22  5102.5 1283.43  5122.5 1284.05  5143.2 1283.64  5172.6 1286.94
  5222.7 1290.98  5233.0 1293.10  5282.8 1295.81  5332.9 1299.78  5378.4 1300.55
#Mann=3,-1,0
  4385.3    0.05       0  5000.5    0.05       0  5004.5    0.05       0
Bank Sta=5000.5,5004.5
Exp/Cntr=0.3,0.1

Type RM Length L Ch R = 1,9238,373,373,373
BEGIN DESCRIPTION:
SANDY 09 14.0
END DESCRIPTION:
XS GIS Cut Line= 3
      2807453.74     10152012.74      2808224.57     10152113.44
      2808356.54     10152144.69
#Sta/Elev= 30
  4326.1 1288.15  4428.9 1285.02  4539.8 1284.68  4620.5 1283.20  4670.9 1281.75
  4701.2 1280.02  4731.5 1280.69  4761.7 1278.99  4829.0 1279.23  4933.2 1278.42
  4953.3 1276.55  4963.4 1272.03  4971.5 1271.88  4971.7 1268.88  4975.2 1268.88
  4975.5 1271.88  4981.8 1272.97  4986.9 1272.64  5003.8 1275.76  5023.9 1276.76
  5094.5 1284.28  5101.5 1286.29  5106.6 1286.29  5114.9 1288.15  5127.0 1291.68
  5135.5 1292.55  5186.8 1294.39  5197.1 1295.15  5206.4 1297.08  5239.1 1296.97
#Mann=3,-1,0
  4326.1    0.05       0  4971.5    0.05       0  4975.5    0.05       0
Bank Sta=4971.5,4975.5
Exp/Cntr=0.3,0.1

Type RM Length L Ch R = 1,8865,215,215,215
BEGIN DESCRIPTION:
SANDY 09 13.0
END DESCRIPTION:
XS GIS Cut Line= 3
      2807305.64     10152153.09      2808037.07     10152443.30
      2808292.33     10152367.41
#Sta/Elev= 30
  4307.3 1293.48  4339.6 1291.69  4361.1 1291.53  4414.9 1288.78  4459.9 1285.71
  4478.9 1285.35  4544.0 1281.69  4597.8 1279.85  4791.5 1277.67  4823.8 1276.57
  4862.3 1276.23  4931.3 1276.84  4940.6 1276.29  4952.9 1274.54  4963.6 1272.02
  4975.7 1267.90  4983.1 1267.88  4983.4 1264.88  4986.9 1264.88  4987.1 1267.88
  5017.4 1271.18  5024.3 1273.15  5029.7 1273.08  5078.4 1277.71  5083.7 1276.36
  5110.4 1278.34  5148.8 1279.73  5228.4 1284.89  5320.0 1288.71  5360.5 1289.52
#Mann=3,-1,0
  4307.3    0.05       0  4983.1    0.05       0  4987.1    0.05       0
Bank Sta=4983.1,4987.1
Exp/Cntr=0.3,0.1

Type RM Length L Ch R = 1,8650,358,358,358
BEGIN DESCRIPTION:
Mapping XS fb06c2a4
END DESCRIPTION:
XS GIS Cut Line= 4
      2807391.29     10152537.76      2807762.77     10152621.08
      2808113.46     10152610.66      2808282.18     10152579.67
#Sta/Elev= 30
  4454.5 1282.06  4460.1 1281.39  4498.3 1281.56  4612.7 1274.77  4674.2 1272.50
  4705.0 1272.45  4715.2 1271.97  4756.2 1272.84  4787.0 1272.89  4822.2 1272.24
  4848.1 1272.90  4934.1 1271.18  4939.1 1271.66  4968.2 1271.64  4988.2 1267.82
  4996.2 1264.72  4996.4 1261.72  4999.9 1261.72  5000.2 1264.72  5008.2 1265.44
  5058.2 1272.51  5088.2 1274.35  5184.7 1278.64  5196.8 1278.64  5208.7 1279.48
  5255.0 1280.75  5260.0 1281.34  5300.2 1281.64  5330.7 1282.54  5357.6 1282.25
#Mann=3,-1,0
  4454.5    0.05       0  4996.2    0.05       0  5000.2    0.05       0
Bank Sta=4996.2,5000.2
Exp/Cntr=0.3,0.1

Type RM Length L Ch R = 1,8292,593,593,593
BEGIN DESCRIPTION:
SANDY 09 12.0
END DESCRIPTION:
XS GIS Cut Line= 3
      2807386.01     10152928.37      2808019.71     10152909.27
      2808271.93     10152750.34
#Sta/Elev= 30
  4502.9 1273.11  4514.5 1273.01  4532.6 1271.39  4562.6 1270.15  4572.6 1270.37
  4612.6 1269.36  4632.6 1269.54  4802.7 1267.48  4872.7 1267.42  4882.7 1266.75
  4892.8 1267.50  4912.8 1267.72  4932.8 1266.95  4942.8 1265.17  4952.8 1264.56
  4962.8 1265.88  4972.8 1265.48  4990.8 1262.86  4991.0 1259.86  4994.5 1259.86
  4994.8 1262.86  5032.8 1265.16  5052.8 1267.26  5102.8 1266.91  5190.3 1270.34
  5196.2 1269.78  5269.2 1273.99  5297.6 1275.08  5363.4 1275.68  5435.0 1277.55
#Mann=3,-1,0
  4502.9    0.05       0  4990.8    0.03       0  4994.8    0.05       0
Bank Sta=4990.8,4994.8
Exp/Cntr=0.3,0.1

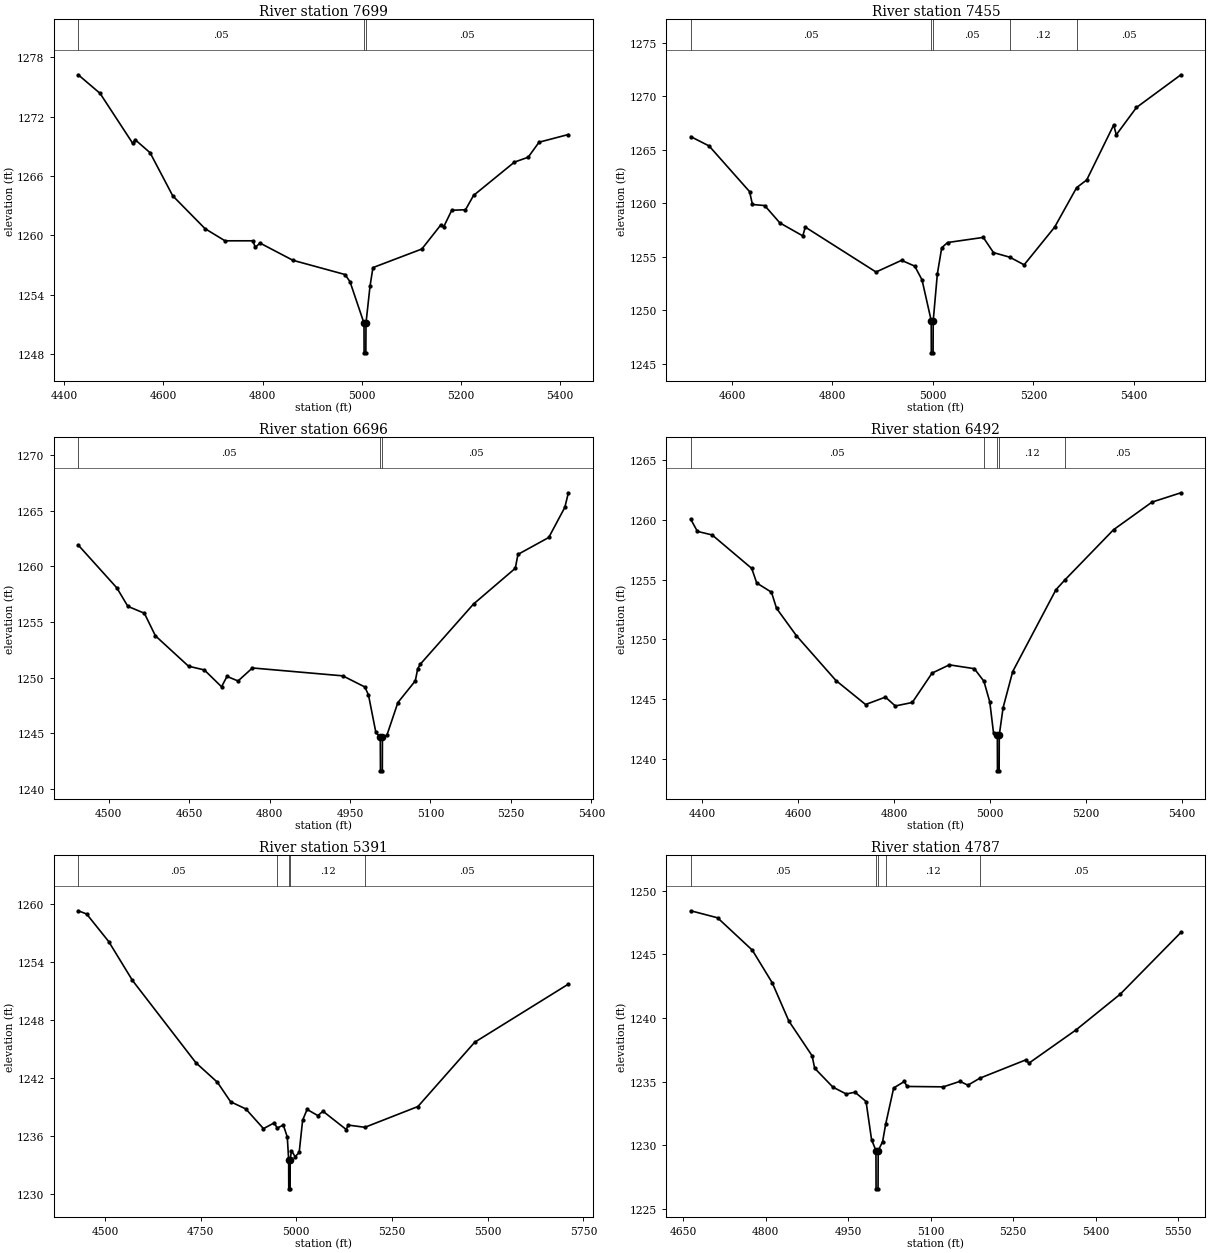
Type RM Length L Ch R = 1,7699,244,244,244
BEGIN DESCRIPTION:
SANDY 09 11.0
END DESCRIPTION:
XS GIS Cut Line= 3
      2807202.04     10153414.49      2807884.29     10153499.55
      2808149.93     10153358.92
#Sta/Elev= 30
  4428.2 1276.23  4472.2 1274.35  4538.0 1269.30  4543.0 1269.66  4573.0 1268.35
  4618.7 1263.99  4683.8 1260.67  4724.1 1259.44  4780.2 1259.44  4785.2 1258.78
  4794.7 1259.21  4860.9 1257.47  4966.0 1256.03  4976.1 1255.30  5004.3 1251.11
  5004.5 1248.11  5008.0 1248.11  5008.3 1251.11  5016.4 1254.84  5022.3 1256.73
  5120.9 1258.61  5159.2 1261.05  5164.9 1260.85  5181.2 1262.53  5208.9 1262.58
  5225.2 1264.03  5307.6 1267.40  5335.2 1267.89  5357.2 1269.41  5416.3 1270.19
#Mann=3,-1,0
  4428.2    0.05       0  5004.3    0.05       0  5008.3    0.05       0
Bank Sta=5004.3,5008.3
Exp/Cntr=0.3,0.1

Type RM Length L Ch R = 1,7455,759,759,759
BEGIN DESCRIPTION:
Mapping XS 68bb22be
END DESCRIPTION:
XS GIS Cut Line= 3
      2807259.32     10153730.45      2807587.42     10153697.47
      2808222.67     10153811.71
#Sta/Elev= 30
  4518.1 1266.22  4554.6 1265.35  4635.1 1261.09  4640.8 1259.89  4665.2 1259.79
  4695.4 1258.17  4741.0 1256.96  4746.0 1257.78  4886.7 1253.59  4937.5 1254.68
  4963.7 1254.14  4978.2 1252.86  4996.5 1249.05  4996.7 1246.05  5000.2 1246.05
  5000.5 1249.05  5008.7 1253.41  5017.4 1255.85  5029.0 1256.34  5100.1 1256.82
  5120.4 1255.40  5153.0 1254.97  5181.4 1254.26  5242.1 1257.78  5285.8 1261.46
  5305.9 1262.18  5359.6 1267.31  5364.7 1266.39  5404.9 1268.94  5493.3 1271.99
#Mann=5,-1,0
  4518.1    0.05       0  4996.5    0.05       0  5000.5    0.05       0
  5153.0    0.12       0  5285.8    0.05       0
Bank Sta=4996.5,5000.5
Exp/Cntr=0.3,0.1

Type RM Length L Ch R = 1,6696,204,204,204
BEGIN DESCRIPTION:
SANDY 09 10.0
END DESCRIPTION:
XS GIS Cut Line= 3
      2807305.65     10154103.10      2807917.28     10154247.81
      2808202.24     10154263.36
#Sta/Elev= 30
  4443.3 1261.92  4515.3 1258.07  4535.8 1256.41  4566.6 1255.79  4587.2 1253.76
  4648.9 1251.03  4678.4 1250.69  4710.5 1249.18  4720.7 1250.11  4741.3 1249.70
  4768.1 1250.87  4936.6 1250.16  4977.7 1249.16  4984.5 1248.44  4998.2 1245.08
  5006.5 1244.62  5006.8 1241.62  5010.3 1241.62  5010.5 1244.62  5018.8 1244.82
  5039.3 1247.76  5071.8 1249.71  5076.3 1250.81  5081.3 1251.22  5180.4 1256.62
  5258.2 1259.83  5263.2 1261.08  5320.6 1262.60  5350.6 1265.31  5357.2 1266.62
#Mann=3,-1,0
  4443.3    0.05       0  5006.5    0.05       0  5010.5    0.05       0
Bank Sta=5006.5,5010.5
Exp/Cntr=0.3,0.1

Type RM Length L Ch R = 1,6492,1101,1101,1101
BEGIN DESCRIPTION:
SANDY 09 9.0
END DESCRIPTION:
XS GIS Cut Line= 3
      2807212.40     10154286.00      2807773.18     10154426.63
      2808215.86     10154442.26
#Sta/Elev= 30
  4376.4 1260.04  4390.2 1259.03  4421.0 1258.73  4503.4 1255.93  4513.8 1254.71
  4544.5 1253.94  4555.1 1252.59  4596.3 1250.31  4678.8 1246.55  4740.6 1244.54
  4781.9 1245.16  4802.5 1244.42  4837.9 1244.71  4879.1 1247.17  4915.1 1247.86
  4967.1 1247.54  4987.1 1246.49  4999.3 1244.76  5007.1 1242.17  5015.1 1241.99
  5015.3 1238.99  5018.8 1238.99  5019.1 1241.99  5027.1 1244.28  5047.1 1247.30
  5137.2 1254.15  5155.9 1254.97  5257.2 1259.17  5337.3 1261.48  5397.5 1262.26
#Mann=5,-1,0
  4376.4    0.05       0  4987.1    0.12       0  5015.1    0.07       0
  5019.1    0.12       0  5155.9    0.05       0
Bank Sta=5015.1,5019.1
Exp/Cntr=0.3,0.1

Type RM Length L Ch R = 1,5391,604,604,604
BEGIN DESCRIPTION:
Mapping XS 624bb061
END DESCRIPTION:
XS GIS Cut Line= 3
      2807195.05     10154296.39      2807387.77     10155001.29
      2807906.89     10155181.85
#Sta/Elev= 30
  4430.3 1259.34  4452.2 1259.01  4509.8 1256.16  4572.0 1252.13  4737.9 1243.60
  4793.9 1241.59  4828.4 1239.57  4868.1 1238.83  4914.2 1236.79  4942.3 1237.39
  4950.0 1236.85  4966.0 1237.16  4976.4 1235.93  4980.0 1233.56  4980.3 1230.56
  4983.8 1230.56  4984.0 1233.56  4987.2 1234.51  4997.1 1233.89  5007.5 1234.33
  5016.5 1237.67  5028.2 1238.78  5056.2 1238.14  5069.7 1238.59  5130.4 1236.70
  5135.6 1237.16  5179.2 1236.93  5317.7 1239.08  5465.9 1245.73  5710.7 1251.75
#Mann=5,-1,0
  4430.3    0.05       0  4950.0    0.12       0  4980.0    0.07       0
  4984.0    0.12       0  5179.2    0.05       0
Bank Sta=4980,4984
Exp/Cntr=0.3,0.1

Type RM Length L Ch R = 1,4787,248,248,248
BEGIN DESCRIPTION:
SANDY 09 8.0
END DESCRIPTION:
XS GIS Cut Line= 3
      2806854.76     10154968.29      2807045.75     10155093.30
      2807705.68     10155153.11
#Sta/Elev= 30
  4664.0 1248.41  4712.7 1247.86  4775.9 1245.32  4812.1 1242.76  4842.3 1239.76
  4884.5 1237.04  4889.2 1236.06  4922.3 1234.58  4946.5 1234.04  4962.5 1234.18
  4982.6 1233.45  4992.6 1230.46  5000.6 1229.60  5000.8 1226.60  5004.4 1226.60
  5004.7 1229.60  5012.7 1230.30  5018.2 1231.66  5032.8 1234.51  5052.1 1235.02
  5057.1 1234.63  5123.1 1234.60  5153.3 1235.03  5167.7 1234.73  5189.5 1235.28
  5273.3 1236.72  5278.4 1236.45  5364.1 1239.06  5444.4 1241.86  5554.9 1246.71
#Mann=5,-1,0
  4664.0    0.05       0  5000.6    0.05       0  5004.7    0.05       0
  5018.2    0.12       0  5189.5    0.05       0
Bank Sta=5000.6,5004.7
Exp/Cntr=0.3,0.1

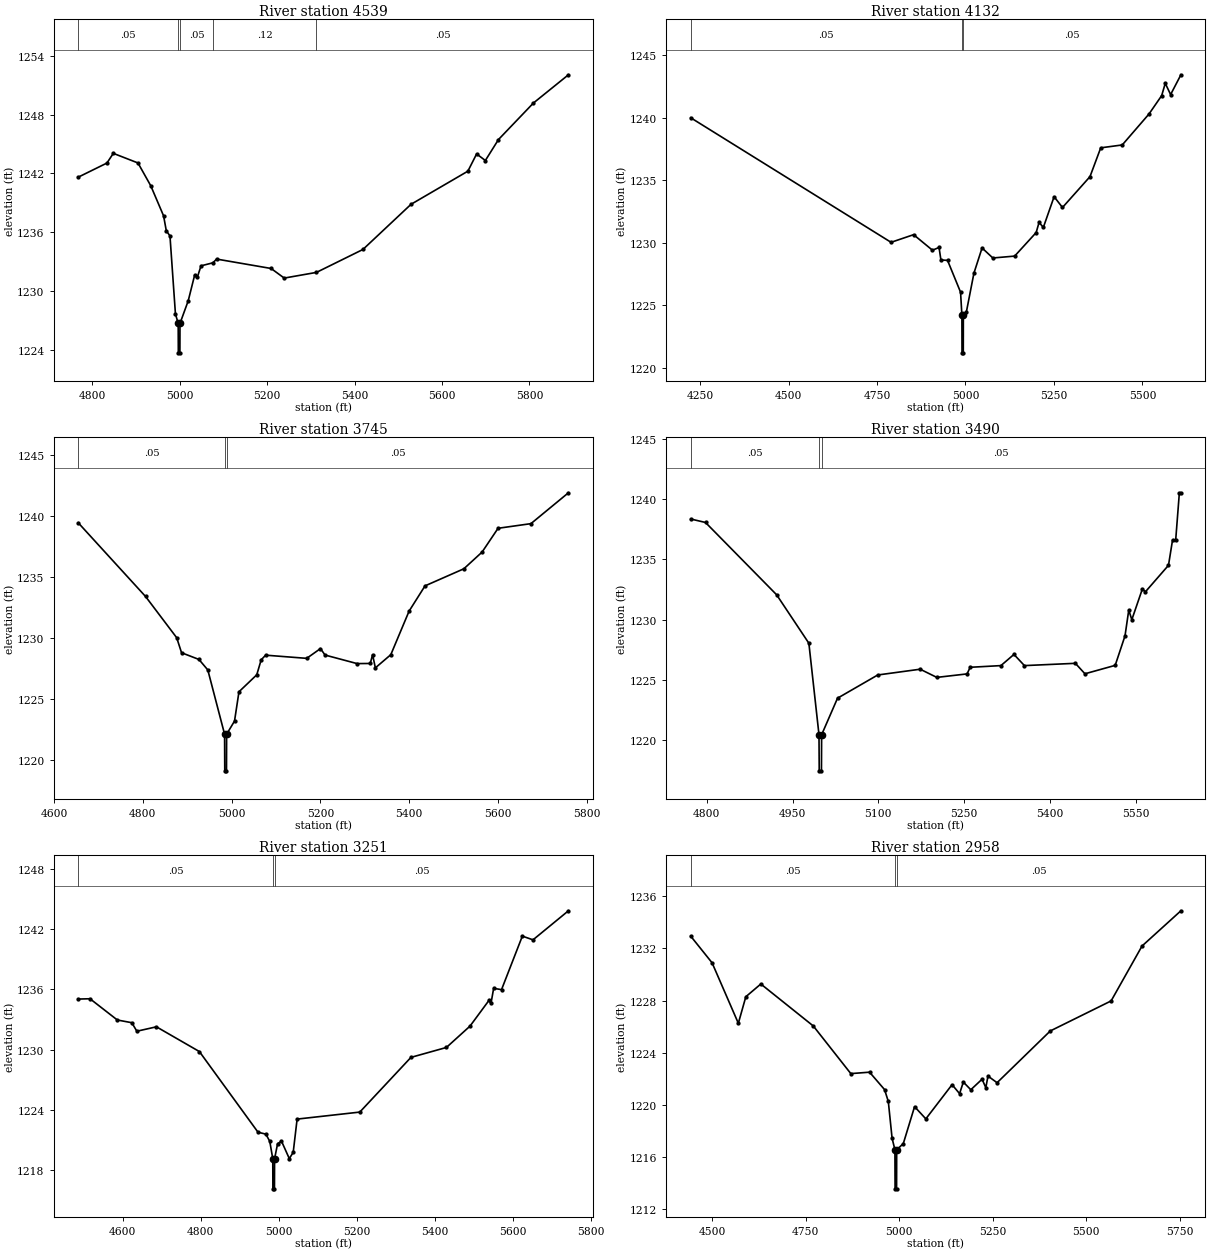
Type RM Length L Ch R = 1,4539,407,407,407
BEGIN DESCRIPTION:
SANDY 09 7.0
END DESCRIPTION:
XS GIS Cut Line= 3
      2806816.55     10155100.22      2807156.86     10155350.24
      2807855.67     10155353.11
#Sta/Elev= 30
  4768.0 1241.62  4833.6 1243.06  4848.2 1244.05  4904.6 1243.07  4933.9 1240.74
  4963.2 1237.67  4969.4 1236.15  4977.8 1235.62  4990.3 1227.66  4996.6 1226.69
  4996.9 1223.69  5000.5 1223.69  5000.7 1226.69  5019.6 1229.01  5034.2 1231.62
  5040.4 1231.40  5048.8 1232.57  5076.1 1232.88  5084.4 1233.26  5209.1 1232.30
  5239.1 1231.32  5312.8 1231.90  5419.1 1234.24  5529.1 1238.85  5659.1 1242.23
  5679.1 1243.99  5699.1 1243.32  5729.1 1245.46  5809.1 1249.19  5889.1 1252.07
#Mann=5,-1,0
  4768.0    0.05       0  4996.6    0.03       0  5000.7    0.05       0
  5076.1    0.12       0  5312.8    0.05       0
Bank Sta=4996.6,5000.7
Exp/Cntr=0.3,0.1

Type RM Length L Ch R = 1,4132,387,387,387
BEGIN DESCRIPTION:
Mapping XS d83ea7a0
END DESCRIPTION:
XS GIS Cut Line= 4
      2806589.15     10155107.19      2806967.63     10155530.80
      2807254.09     10155636.70      2807759.29     10155553.37
#Sta/Elev= 30
  4223.4 1239.98  4789.7 1230.04  4853.4 1230.65  4906.7 1229.41  4925.3 1229.63
  4930.6 1228.63  4949.3 1228.60  4986.1 1226.06  4989.9 1224.22  4990.2 1221.22
  4993.8 1221.22  4994.0 1224.22  5002.6 1224.49  5023.9 1227.58  5046.9 1229.59
  5077.3 1228.79  5139.0 1228.94  5199.8 1230.82  5208.0 1231.63  5220.1 1231.23
  5250.5 1233.68  5274.2 1232.82  5351.9 1235.28  5382.3 1237.58  5443.1 1237.81
  5518.7 1240.28  5554.6 1241.75  5564.7 1242.73  5579.8 1241.83  5608.9 1243.41
#Mann=3,-1,0
  4223.4    0.05       0  4989.9    0.05       0  4994.0    0.05       0
Bank Sta=4989.9,4994
Exp/Cntr=0.3,0.1

Type RM Length L Ch R = 1,3745,255,255,255
BEGIN DESCRIPTION:
SANDY 09 6.0
END DESCRIPTION:
XS GIS Cut Line= 3
      2806634.27     10155792.95      2807061.38     10155765.18
      2807717.66     10155600.24
#Sta/Elev= 30
  4654.4 1239.43  4806.1 1233.39  4876.3 1230.01  4887.2 1228.78  4926.4 1228.23
  4946.4 1227.37  4984.2 1222.10  4984.6 1219.10  4988.5 1219.10  4988.8 1222.10
  5006.6 1223.18  5016.6 1225.58  5056.7 1226.97  5066.7 1228.20  5076.7 1228.58
  5169.3 1228.32  5200.3 1229.12  5210.6 1228.59  5282.8 1227.89  5312.5 1227.90
  5317.7 1228.62  5324.0 1227.54  5358.8 1228.62  5400.0 1232.19  5435.9 1234.26
  5523.4 1235.66  5564.5 1237.03  5600.5 1238.98  5674.6 1239.36  5759.1 1241.89
#Mann=3,-1,0
  4654.4    0.05       0  4984.2    0.05       0  4988.8    0.05       0
Bank Sta=4984.2,4988.8
Exp/Cntr=0.3,0.1

Type RM Length L Ch R = 1,3490,239,239,239
BEGIN DESCRIPTION:
SANDY 09 5.0
END DESCRIPTION:
XS GIS Cut Line= 3
      2806689.88     10156030.80      2807035.34     10156001.29
      2807505.67     10155803.12
#Sta/Elev= 30
  4772.0 1238.36  4797.9 1238.07  4922.2 1232.06  4978.6 1228.03  4996.3 1220.42
  4996.7 1217.42  5000.6 1217.42  5000.9 1220.42  5028.7 1223.46  5099.0 1225.39
  5173.2 1225.87  5202.3 1225.19  5255.2 1225.48  5260.6 1226.03  5314.4 1226.17
  5337.2 1227.10  5355.5 1226.17  5444.6 1226.36  5461.3 1225.49  5514.2 1226.19
  5531.4 1228.65  5537.9 1230.78  5543.3 1229.99  5561.7 1232.54  5567.1 1232.31
  5607.4 1234.51  5614.5 1236.62  5620.0 1236.62  5626.4 1240.54  5629.1 1240.54
#Mann=3,-1,0
  4772.0    0.05       0  4996.3    0.05       0  5000.9    0.05       0
Bank Sta=4996.3,5000.9
Exp/Cntr=0.3,0.1

Type RM Length L Ch R = 1,3251,293,293,293
BEGIN DESCRIPTION:
SANDY 09 4.0
END DESCRIPTION:
XS GIS Cut Line= 3
      2806505.64     10156203.11      2807169.02     10156226.98
      2807755.68     10156153.11
#Sta/Elev= 30
  4486.6 1235.04  4516.7 1235.07  4586.7 1232.95  4623.7 1232.68  4636.7 1231.83
  4686.8 1232.27  4796.8 1229.80  4946.9 1221.75  4967.0 1221.56  4977.0 1220.84
  4984.7 1219.10  4985.0 1216.10  4989.0 1216.10  4989.3 1219.10  4997.0 1220.60
  5007.0 1220.86  5027.0 1219.12  5037.0 1219.74  5047.0 1223.06  5207.5 1223.76
  5338.5 1229.22  5429.3 1230.21  5489.7 1232.34  5538.3 1234.91  5543.4 1234.60
  5550.2 1236.11  5570.4 1235.98  5623.7 1241.32  5651.0 1240.95  5741.7 1243.85
#Mann=3,-1,0
  4486.6    0.05       0  4984.7    0.03       0  4989.3    0.05       0
Bank Sta=4984.7,4989.3
Exp/Cntr=0.3,0.1

Type RM Length L Ch R = 1,2958,585,585,585
BEGIN DESCRIPTION:
SANDY 09 3.0
END DESCRIPTION:
XS GIS Cut Line= 3
      2806328.71     10156435.31      2807189.85     10156492.61
      2807627.33     10156400.60
#Sta/Elev= 30
  4442.8 1232.95  4499.9 1230.90  4570.1 1226.25  4590.1 1228.29  4630.2 1229.27
  4770.5 1226.04  4870.7 1222.38  4920.8 1222.49  4960.9 1221.15  4970.9 1220.24
  4981.0 1217.41  4988.6 1216.52  4989.0 1213.52  4993.0 1213.52  4993.3 1216.52
  5011.0 1217.00  5041.1 1219.84  5071.2 1218.90  5141.3 1221.53  5161.4 1220.84
  5171.4 1221.73  5191.4 1221.14  5221.5 1221.95  5231.5 1221.30  5237.3 1222.19
  5261.6 1221.68  5403.8 1225.66  5566.4 1227.97  5649.0 1232.19  5752.9 1234.90
#Mann=3,-1,0
  4442.8    0.05       0  4988.6    0.05       0  4993.3    0.05       0
Bank Sta=4988.6,4993.3
Exp/Cntr=0.3,0.1

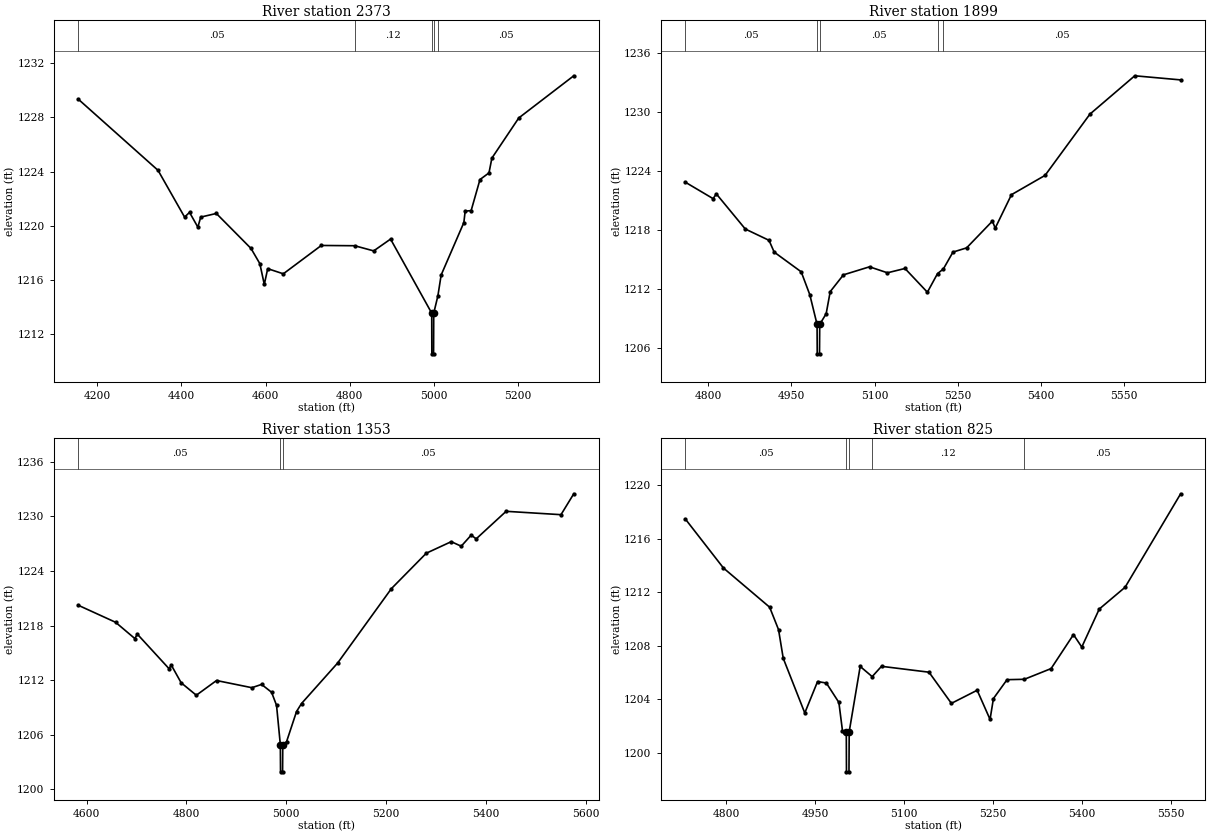
Type RM Length L Ch R = 1,2373,474,474,474
BEGIN DESCRIPTION:
SANDY 09 2.0
END DESCRIPTION:
XS GIS Cut Line= 4
      2806386.06     10156607.20      2806995.40     10156806.84
      2807266.72     10156823.64      2807448.51     10157015.15
#Sta/Elev= 30
  4155.3 1229.33  4344.3 1224.10  4407.5 1220.65  4419.2 1221.00  4439.0 1219.91
  4445.8 1220.65  4482.9 1220.92  4565.3 1218.34  4586.3 1217.22  4596.9 1215.69
  4605.0 1216.85  4642.1 1216.47  4732.4 1218.56  4811.7 1218.54  4856.9 1218.16
  4897.0 1219.03  4994.8 1213.57  4995.1 1210.57  4999.2 1210.57  4999.6 1213.57
  5009.5 1214.85  5017.2 1216.38  5071.2 1220.25  5074.3 1221.09  5088.5 1221.13
  5109.5 1223.42  5130.9 1223.91  5137.8 1225.00  5201.7 1227.96  5332.4 1231.07
#Mann=5,-1,0
  4155.3    0.05       0  4811.7    0.12       0  4994.8    0.07       0
  4999.6    0.12       0  5009.5    0.05       0
Bank Sta=4994.8,4999.6
Exp/Cntr=0.3,0.1

Type RM Length L Ch R = 1,1899,546,546,546
BEGIN DESCRIPTION:
Mapping XS 0485d078
END DESCRIPTION:
XS GIS Cut Line= 4
      2806629.13     10156921.45      2806873.88     10157070.73
      2806964.15     10157034.27      2807467.60     10157105.45
#Sta/Elev= 30
  4759.1 1222.87  4809.0 1221.20  4814.9 1221.68  4867.1 1218.10  4909.8 1216.95
  4919.1 1215.75  4967.8 1213.74  4983.3 1211.41  4996.4 1208.38  4996.7 1205.38
  5000.8 1205.38  5001.2 1208.38  5012.8 1209.47  5020.1 1211.72  5043.9 1213.43
  5090.9 1214.25  5123.2 1213.64  5154.8 1214.08  5195.2 1211.66  5213.5 1213.56
  5224.0 1214.03  5241.3 1215.75  5265.9 1216.18  5312.4 1218.91  5317.4 1218.19
  5346.7 1221.60  5407.3 1223.57  5488.1 1229.81  5568.9 1233.72  5651.6 1233.30
#Mann=5,-1,0
  4759.1    0.05       0  4996.4    0.05       0  5001.2    0.05       0
  5213.5    0.12       0  5224.0    0.05       0
Bank Sta=4996.4,5001.2
Exp/Cntr=0.3,0.1

Type RM Length L Ch R = 1,1353,528,528,528
BEGIN DESCRIPTION:
Mapping XS eb68d953
END DESCRIPTION:
XS GIS Cut Line= 4
      2806582.25     10157230.46      2806875.61     10157275.59
      2807097.84     10157287.74      2807571.25     10157284.28
#Sta/Elev= 30
  4583.5 1220.22  4657.8 1218.36  4696.4 1216.57  4701.5 1217.05  4764.7 1213.27
  4769.8 1213.62  4789.3 1211.70  4819.7 1210.33  4860.2 1211.95  4931.0 1211.16
  4950.5 1211.52  4970.5 1210.66  4980.5 1209.22  4988.1 1204.90  4988.5 1201.90
  4992.6 1201.90  4993.0 1204.90  5000.6 1205.22  5020.6 1208.54  5030.6 1209.42
  5102.9 1213.87  5210.7 1222.06  5280.7 1225.96  5330.7 1227.23  5350.7 1226.73
  5370.7 1227.95  5380.7 1227.54  5440.7 1230.57  5550.7 1230.20  5576.3 1232.50
#Mann=3,-1,0
  4583.5    0.05       0  4988.1    0.05       0  4993.0    0.05       0
Bank Sta=4988.1,4993
Exp/Cntr=0.3,0.1

Type RM Length L Ch R = 1,825,0,0,0
BEGIN DESCRIPTION:
SANDY 09 1.0
END DESCRIPTION:
XS GIS Cut Line= 3
      2806599.58     10157570.73      2806894.71     10157772.12
      2807311.02     10158004.56
#Sta/Elev= 30
  4731.6 1217.46  4795.7 1213.80  4873.5 1210.87  4888.5 1209.19  4896.4 1207.05
  4932.7 1202.96  4954.2 1205.31  4969.0 1205.20  4990.1 1203.75  4996.2 1201.62
  5002.6 1201.56  5002.9 1198.56  5007.1 1198.56  5007.5 1201.56  5026.0 1206.44
  5046.2 1205.68  5061.9 1206.45  5141.9 1206.01  5179.6 1203.68  5223.0 1204.66
  5244.7 1202.48  5250.4 1204.04  5273.3 1205.45  5302.5 1205.48  5347.5 1206.28
  5385.2 1208.82  5399.2 1207.89  5428.6 1210.73  5472.1 1212.36  5565.7 1219.35
#Mann=5,-1,0
  4731.6    0.05       0  5002.6    0.05       0  5007.5    0.05       0
  5046.2    0.12       0  5302.5    0.05       0
Bank Sta=5002.6,5007.5
Exp/Cntr=0.3,0.1

Chan Stop Cuts=-1