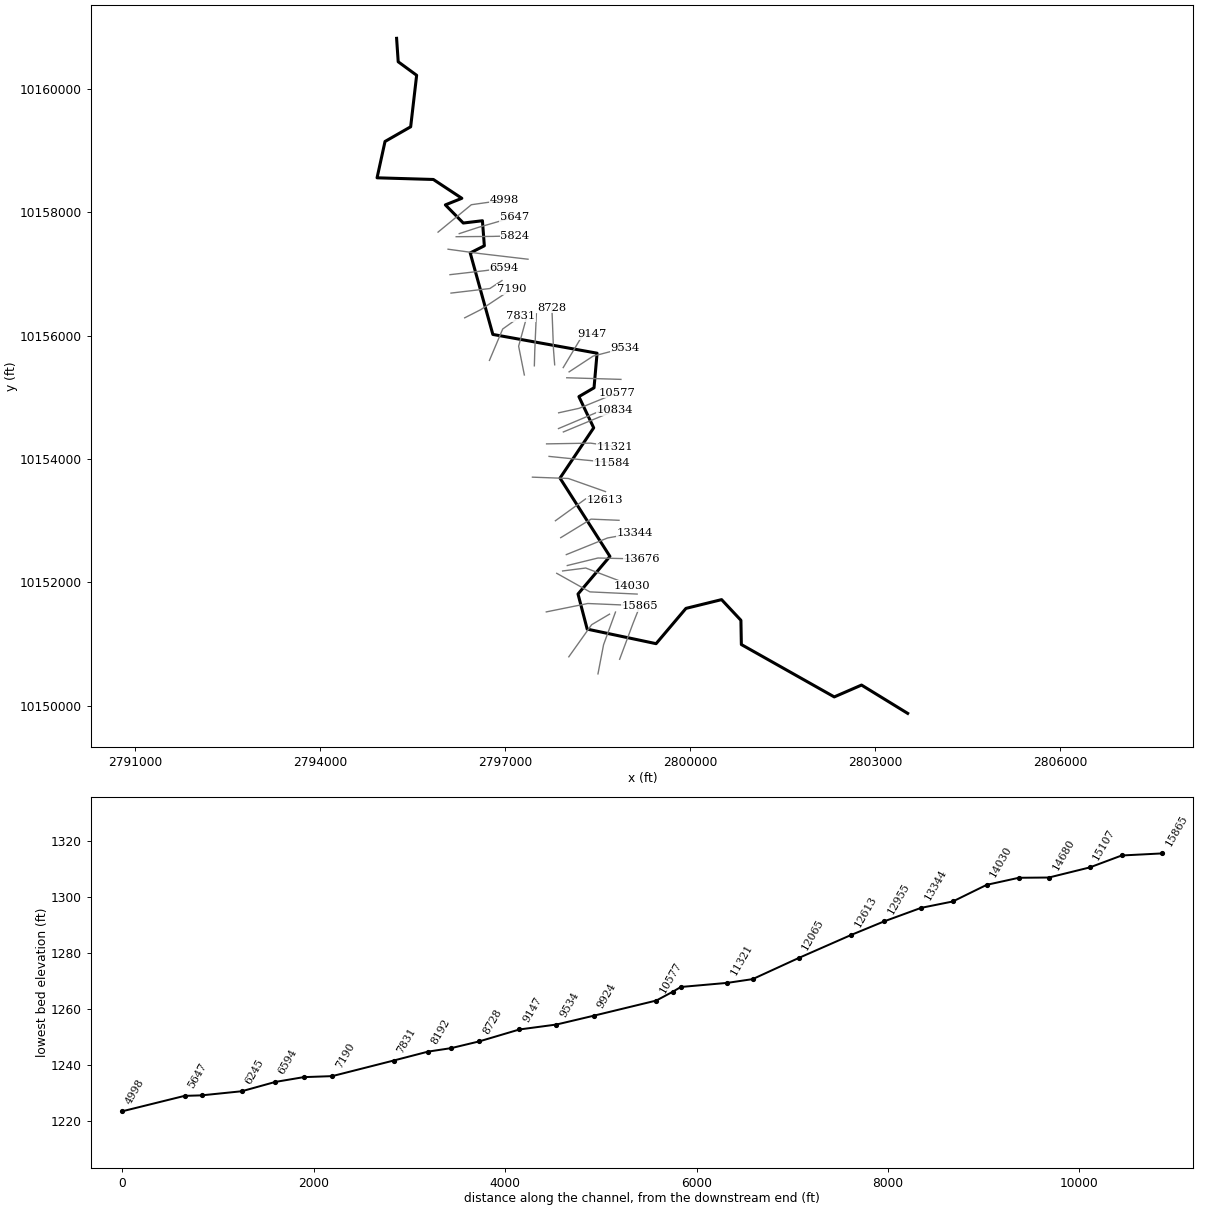
--- SANDY 10.prj (project) ---

Proj Title=SANDY 10 Base Level Engineering
Current Plan=p01
Default Exp/Contr=0.3,0.1
English Units
Geom File=g01
Flow File=f01
Plan File=p01
BEGIN DESCRIPTION:
SANDY 10
END DESCRIPTION:

--- SANDY 10.p01 (plan) ---

Plan Title=Multiple Run
Short Identifier=Multiple
Geom File=g01
Flow File=f01
Subcritical Flow
K Sum by GR= 0
Std Step Tol= 0.01
Critical Tol= 0.01
Num of Std Step Trials= 20
Max Error Tol= 0.3
Flow Tol Ratio= 0.001
Split Flow NTrial= 30
Split Flow Tol= 0.02
Split Flow Ratio= 0.02
Log Output Level= 0
Friction Slope Method= 1
Unsteady Friction Slope Method= 2
Unsteady Bridges Friction Slope Method= 1
Parabolic Critical Depth
Global Vel Dist=  1 , 1 , 1
Global Log Level= 0
CheckData=True
Encroach Param= -1, 0, 0, 0
BEGIN DESCRIPTION:
Multiple Run
END DESCRIPTION:

--- SANDY 10.f01 (steady flow) ---

Flow Title=Multiple
Number of Profiles=7
Profile Names=10-year,25-year,50-year,1pct_min,100-year,1pct_plu,500-year
River Rch & RM= SANDY 10,Reach-1,15865
     102     206     331     175     530    1599    1448
River Rch & RM= SANDY 10,Reach-1,8728
     132     277     450     241     729    2202    2037
Boundary for River Rch & Prof#=SANDY 10,Reach-1,1
Up Type=0
Dn Type=3
Dn Slope=0.005
Boundary for River Rch & Prof#=SANDY 10,Reach-1,2
Up Type=0
Dn Type=3
Dn Slope=0.005
Boundary for River Rch & Prof#=SANDY 10,Reach-1,3
Up Type=0
Dn Type=3
Dn Slope=0.005
Boundary for River Rch & Prof#=SANDY 10,Reach-1,4
Up Type=0
Dn Type=3
Dn Slope=0.005
Boundary for River Rch & Prof#=SANDY 10,Reach-1,5
Up Type=0
Dn Type=3
Dn Slope=0.005
Boundary for River Rch & Prof#=SANDY 10,Reach-1,6
Up Type=0
Dn Type=3
Dn Slope=0.005
Boundary for River Rch & Prof#=SANDY 10,Reach-1,7
Up Type=0
Dn Type=3
Dn Slope=0.005

--- SANDY 10.g01 (geometry) ---

Geom Title=Existing Conditions

River Reach=SANDY 10,Reach-1
Reach XY= 30
      2803525.00     10149876.00      2802776.75     10150335.00
      2802334.75     10150143.00      2800828.75     10150992.00
      2800821.50     10151385.00      2800508.25     10151720.00
      2799930.50     10151578.00      2799446.50     10151006.00
      2798329.50     10151242.00      2798180.75     10151811.00
      2798698.00     10152421.00      2797888.75     10153690.00
      2798435.00     10154505.00      2798195.25     10155011.00
      2798440.50     10155154.00      2798489.75     10155715.00
      2796800.25     10156019.00      2796433.25     10157340.00
      2796662.25     10157456.00      2796631.25     10157862.00
      2796321.00     10157825.00      2796030.50     10158119.00
      2796297.75     10158226.00      2795835.75     10158531.00
      2794923.25     10158558.00      2795052.25     10159147.00
      2795468.00     10159385.00      2795564.75     10160220.00
      2795266.00     10160439.00      2795240.00     10160819.00

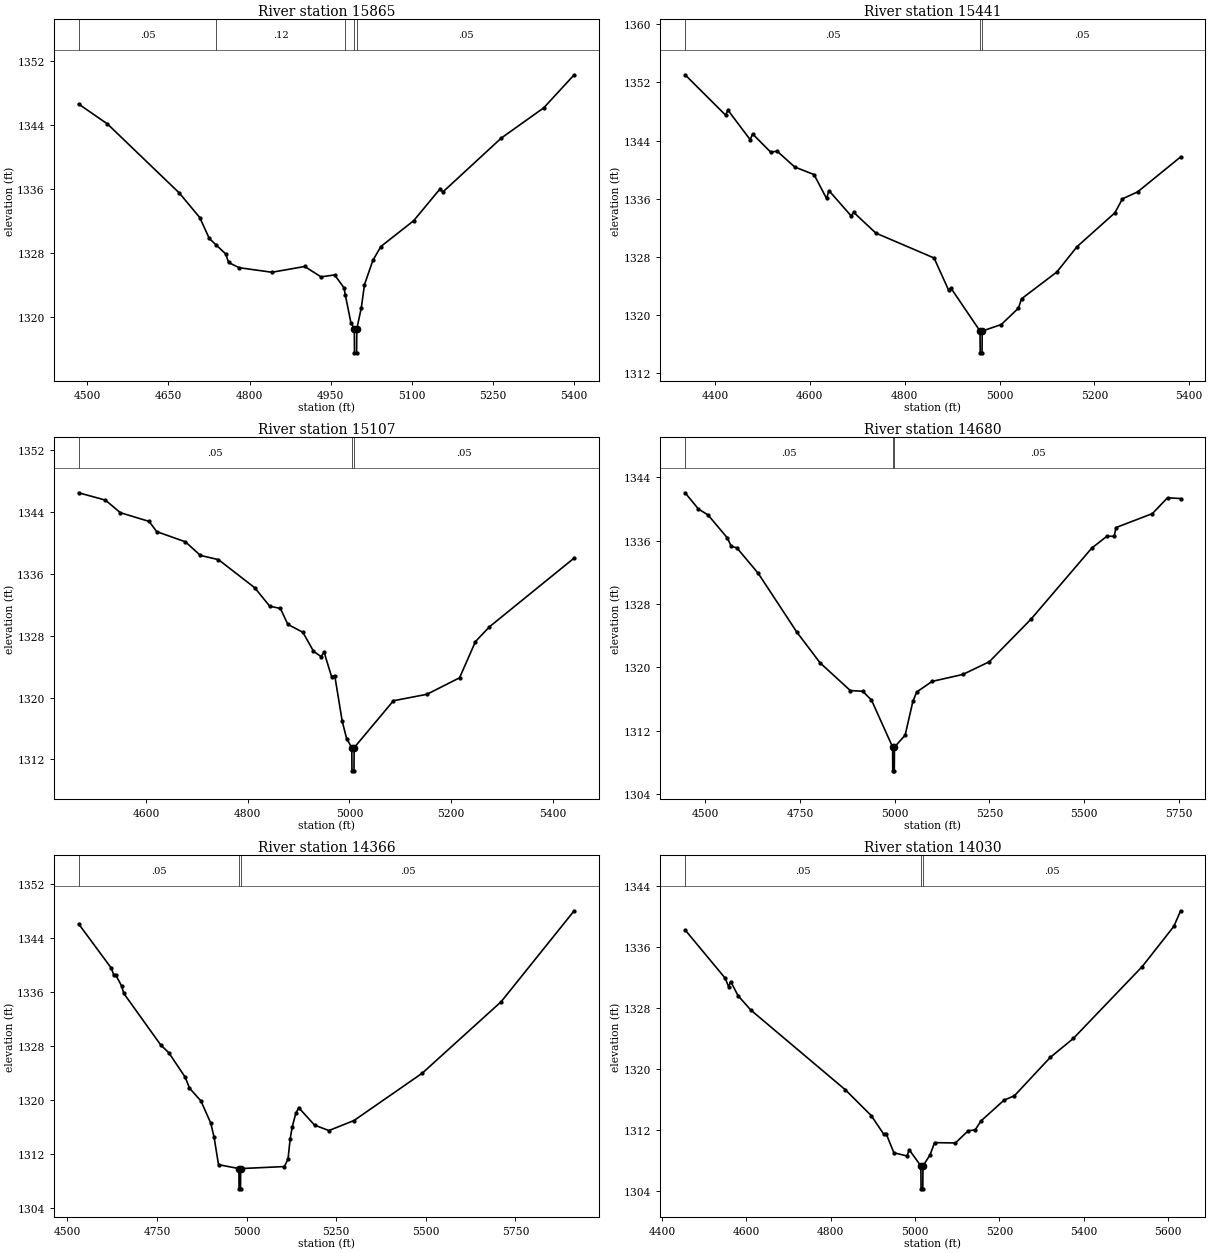
Type RM Length L Ch R = 1,15865,424,424,424
BEGIN DESCRIPTION:
SANDY 10 32.0
END DESCRIPTION:
XS GIS Cut Line= 3
      2798855.70     10150753.14      2799070.03     10151327.71
      2799181.50     10151609.95
#Sta/Elev= 30
  4483.9 1346.63  4537.2 1344.14  4670.2 1335.50  4708.0 1332.43  4725.5 1329.83
  4738.6 1328.98  4755.9 1327.89  4761.4 1326.81  4780.8 1326.16  4841.5 1325.59
  4902.1 1326.31  4932.4 1325.01  4957.4 1325.26  4974.8 1323.65  4977.1 1322.80
  4987.7 1319.24  4993.9 1318.51  4994.2 1315.51  4998.1 1315.51  4998.5 1318.51
  5006.8 1321.13  5012.7 1324.04  5028.2 1327.07  5043.0 1328.81  5103.6 1332.03
  5152.4 1336.01  5157.7 1335.63  5265.9 1342.38  5344.4 1346.16  5400.6 1350.29
#Mann=5,-1,0
  4483.9    0.05       0  4738.6    0.12       0  4977.1    0.05       0
  4993.9    0.05       0  4998.5    0.05       0
Bank Sta=4993.9,4998.5
Exp/Cntr=0.3,0.1

Type RM Length L Ch R = 1,15441,334,334,334
BEGIN DESCRIPTION:
SANDY 10 31.0
END DESCRIPTION:
XS GIS Cut Line= 3
      2798504.28     10150516.10      2798594.98     10150988.73
      2798788.25     10151518.42
#Sta/Elev= 30
  4336.9 1353.06  4422.2 1347.51  4427.3 1348.19  4474.2 1344.12  4479.3 1344.92
  4517.1 1342.42  4531.2 1342.53  4568.1 1340.36  4608.8 1339.32  4635.2 1336.03
  4640.3 1337.11  4687.2 1333.62  4692.3 1334.12  4739.2 1331.26  4862.0 1327.83
  4892.6 1323.41  4897.9 1323.65  4958.9 1317.77  4959.3 1314.77  4963.2 1314.77
  4963.5 1317.77  5003.8 1318.67  5040.0 1320.93  5046.4 1322.21  5120.9 1325.90
  5163.5 1329.39  5243.3 1334.05  5259.3 1335.98  5291.2 1336.93  5382.0 1341.75
#Mann=3,-1,0
  4336.9    0.05       0  4958.9    0.05       0  4963.5    0.05       0
Bank Sta=4958.9,4963.5
Exp/Cntr=0.3,0.1

Type RM Length L Ch R = 1,15107,427,427,427
BEGIN DESCRIPTION:
SANDY 10 30.0
END DESCRIPTION:
XS GIS Cut Line= 3
      2798031.64     10150793.02      2798401.63     10151313.38
      2798691.78     10151484.62
#Sta/Elev= 30
  4466.9 1346.52  4519.6 1345.57  4549.1 1343.94  4605.7 1342.81  4620.5 1341.49
  4677.0 1340.17  4706.6 1338.41  4742.2 1337.86  4813.5 1334.22  4843.1 1331.83
  4864.0 1331.54  4878.7 1329.48  4908.3 1328.45  4929.2 1326.00  4943.9 1325.31
  4950.1 1325.87  4964.8 1322.70  4971.0 1322.85  4985.7 1316.94  4994.4 1314.69
  5004.6 1313.51  5004.9 1310.51  5008.9 1310.51  5009.2 1313.51  5086.6 1319.59
  5152.4 1320.42  5216.7 1322.56  5248.0 1327.25  5275.3 1329.15  5442.3 1338.07
#Mann=3,-1,0
  4466.9    0.05       0  5004.6    0.05       0  5009.2    0.05       0
Bank Sta=5004.6,5009.2
Exp/Cntr=0.3,0.1

Type RM Length L Ch R = 1,14680,314,314,314
BEGIN DESCRIPTION:
SANDY 10 29.0
END DESCRIPTION:
XS GIS Cut Line= 3
      2797666.42     10151521.07      2798339.56     10151657.13
      2798960.25     10151630.87
#Sta/Elev= 30
  4446.9 1342.03  4482.1 1339.98  4507.4 1339.23  4558.4 1336.33  4568.6 1335.28
  4583.6 1335.07  4640.0 1331.85  4742.0 1324.42  4803.2 1320.55  4883.0 1317.05
  4915.5 1316.96  4938.8 1315.86  4994.7 1309.91  4995.0 1306.91  4999.1 1306.91
  4999.5 1309.91  5027.7 1311.41  5048.1 1315.68  5058.3 1316.87  5099.1 1318.21
  5179.8 1319.08  5249.9 1320.69  5360.0 1326.07  5520.1 1335.03  5560.2 1336.54
  5579.4 1336.54  5584.4 1337.64  5680.3 1339.40  5720.3 1341.40  5754.9 1341.30
#Mann=3,-1,0
  4446.9    0.05       0  4994.7    0.03       0  4999.5    0.05       0
Bank Sta=4994.7,4999.5
Exp/Cntr=0.3,0.1

Type RM Length L Ch R = 1,14366,336,336,336
BEGIN DESCRIPTION:
Mapping XS 8a61d53b
END DESCRIPTION:
XS GIS Cut Line= 3
      2797835.91     10152146.48      2798372.98     10151845.72
      2799139.29     10151809.91
#Sta/Elev= 30
  4531.2 1346.06  4622.6 1339.49  4629.3 1338.46  4635.0 1338.46  4651.0 1336.88
  4657.0 1335.78  4760.2 1328.13  4783.1 1326.96  4828.9 1323.32  4840.5 1321.74
  4872.4 1319.84  4899.8 1316.57  4909.2 1314.45  4921.5 1310.40  4978.5 1309.82
  4978.8 1306.82  4982.9 1306.82  4983.3 1309.82  5105.3 1310.12  5115.5 1311.24
  5121.3 1314.14  5127.0 1315.95  5137.3 1318.03  5145.4 1318.83  5189.5 1316.26
  5229.5 1315.45  5299.6 1316.94  5489.8 1323.94  5710.1 1334.53  5913.9 1348.00
#Mann=3,-1,0
  4531.2    0.05       0  4978.5    0.05       0  4983.3    0.05       0
Bank Sta=4978.5,4983.3
Exp/Cntr=0.3,0.1

Type RM Length L Ch R = 1,14030,354,354,354
BEGIN DESCRIPTION:
Mapping XS afa2819c
END DESCRIPTION:
XS GIS Cut Line= 3
      2797931.38     10152184.70      2798306.14     10152232.44
      2799050.83     10151948.41
#Sta/Elev= 30
  4454.7 1338.27  4549.8 1331.93  4557.8 1330.82  4562.9 1331.49  4580.0 1329.66
  4610.2 1327.77  4834.9 1317.28  4895.8 1313.92  4925.9 1311.45  4931.2 1311.56
  4949.7 1309.03  4980.7 1308.61  4986.1 1309.42  5013.7 1307.30  5014.1 1304.30
  5018.2 1304.30  5018.6 1307.30  5035.3 1308.74  5046.2 1310.36  5095.7 1310.32
  5125.8 1311.92  5142.4 1312.03  5155.9 1313.19  5210.7 1315.93  5235.4 1316.51
  5320.3 1321.54  5375.1 1324.03  5538.4 1333.46  5613.3 1338.73  5629.5 1340.78
#Mann=3,-1,0
  4454.7    0.05       0  5013.7    0.05       0  5018.6    0.05       0
Bank Sta=5013.7,5018.6
Exp/Cntr=0.3,0.1

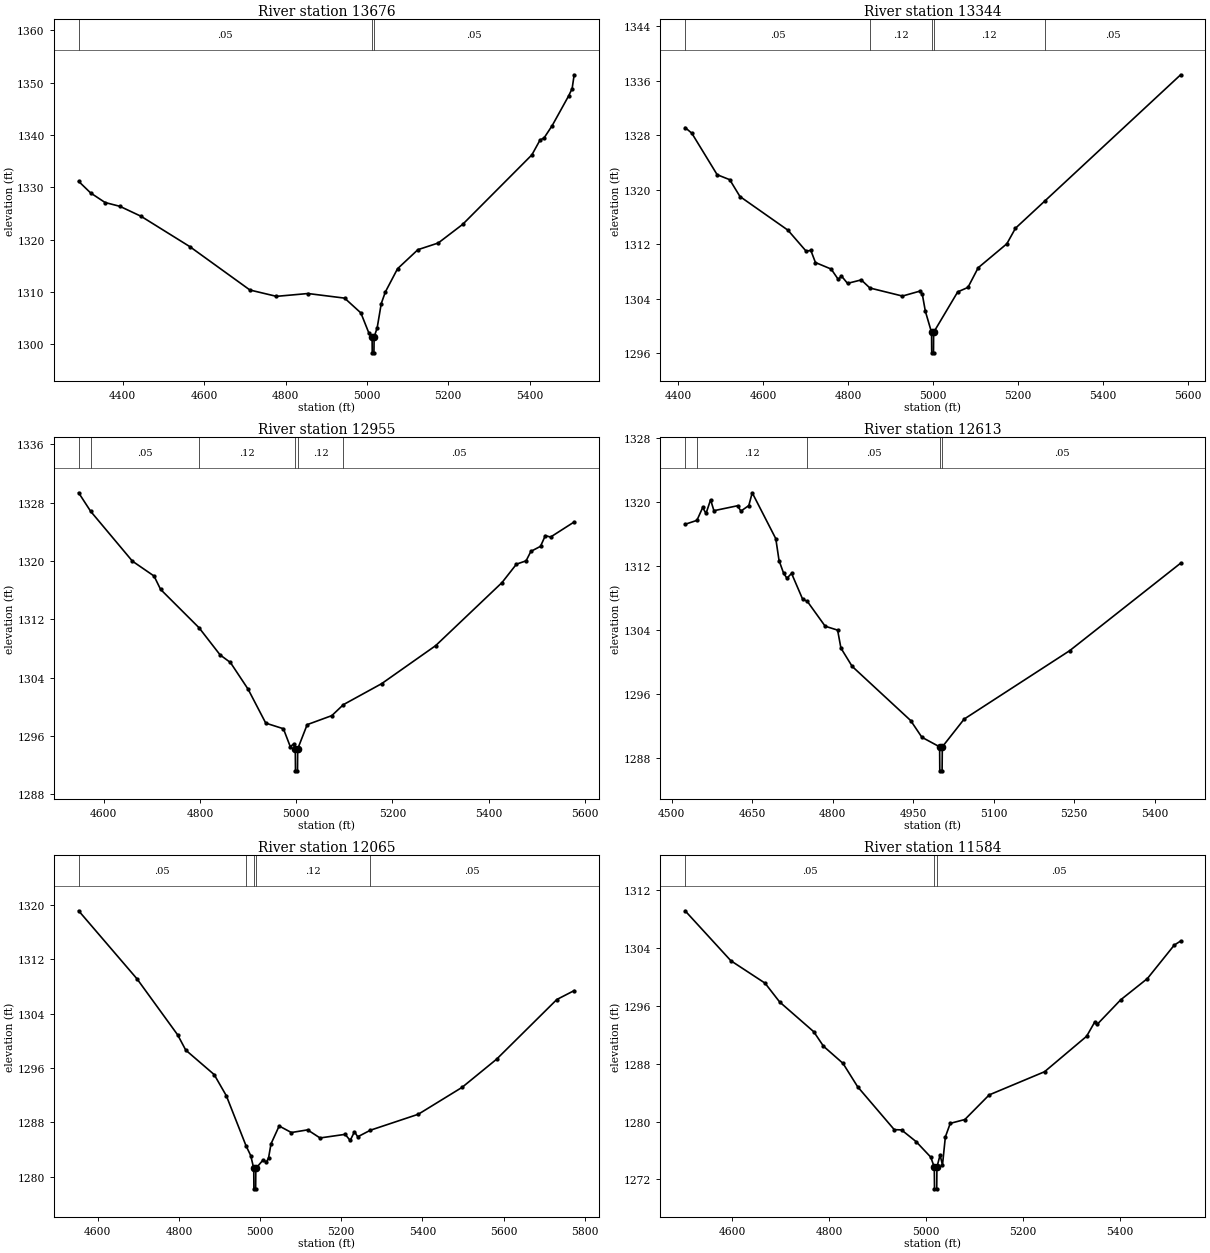
Type RM Length L Ch R = 1,13676,332,332,332
BEGIN DESCRIPTION:
SANDY 10 28.0
END DESCRIPTION:
XS GIS Cut Line= 3
      2798006.94     10152272.77      2798504.27     10152394.76
      2799209.60     10152378.08
#Sta/Elev= 30
  4291.7 1331.16  4321.3 1328.93  4356.7 1327.11  4393.1 1326.38  4445.0 1324.48
  4564.6 1318.69  4712.6 1310.38  4777.7 1309.17  4855.2 1309.71  4945.2 1308.83
  4985.2 1306.00  5005.2 1302.09  5012.8 1301.37  5013.1 1298.37  5017.3 1298.37
  5017.7 1301.37  5025.3 1303.17  5035.3 1307.79  5045.3 1310.00  5075.3 1314.45
  5125.3 1318.09  5175.3 1319.37  5235.3 1322.93  5405.4 1336.22  5425.4 1339.05
  5435.4 1339.46  5455.4 1341.83  5495.4 1347.45  5504.3 1348.89  5509.3 1351.53
#Mann=3,-1,0
  4291.7    0.05       0  5012.8    0.03       0  5017.7    0.05       0
Bank Sta=5012.8,5017.7
Exp/Cntr=0.3,0.1

Type RM Length L Ch R = 1,13344,389,389,389
BEGIN DESCRIPTION:
SANDY 10 27.0
END DESCRIPTION:
XS GIS Cut Line= 3
      2797991.06     10152449.68      2798659.44     10152719.42
      2799098.48     10152798.16
#Sta/Elev= 30
  4416.7 1329.14  4432.5 1328.31  4492.2 1322.22  4521.8 1321.49  4545.9 1319.02
  4658.9 1314.08  4701.6 1311.01  4712.8 1311.11  4723.6 1309.34  4760.6 1308.38
  4777.5 1306.85  4784.8 1307.37  4799.1 1306.28  4831.5 1306.79  4851.8 1305.60
  4928.5 1304.42  4969.9 1305.15  4975.3 1304.66  4982.4 1302.19  4997.0 1299.09
  4997.4 1296.09  5001.6 1296.09  5001.9 1299.09  5058.6 1305.03  5082.7 1305.69
  5106.8 1308.57  5174.3 1312.09  5194.6 1314.37  5263.8 1318.37  5583.5 1336.88
#Mann=5,-1,0
  4416.7    0.05       0  4851.8    0.12       0  4997.0    0.07       0
  5001.9    0.12       0  5263.8    0.05       0
Bank Sta=4997,5001.9
Exp/Cntr=0.3,0.1

Type RM Length L Ch R = 1,12955,342,342,342
BEGIN DESCRIPTION:
SANDY 10 26.0
END DESCRIPTION:
XS GIS Cut Line= 3
      2797900.31     10152724.18      2798392.08     10153024.97
      2798845.61     10153005.88
#Sta/Elev= 30
  4547.7 1329.34  4572.8 1326.79  4659.5 1319.97  4704.5 1317.93  4718.1 1316.10
  4798.1 1310.84  4842.0 1307.11  4863.3 1306.08  4900.0 1302.43  4936.8 1297.77
  4973.5 1297.00  4987.7 1294.56  4994.8 1294.90  4998.2 1294.23  4998.6 1291.23
  5002.8 1291.23  5003.2 1294.23  5022.9 1297.56  5074.2 1298.80  5098.2 1300.30
  5177.8 1303.18  5290.1 1308.39  5428.0 1317.03  5458.1 1319.56  5478.1 1320.01
  5488.1 1321.31  5508.1 1322.00  5518.1 1323.47  5529.0 1323.27  5578.1 1325.34
#Mann=6,-1,0
  4547.7    0.12       0  4572.8    0.05       0  4798.1    0.12       0
  4998.2    0.07       0  5003.2    0.12       0  5098.2    0.05       0
Bank Sta=4998.2,5003.2
Exp/Cntr=0.3,0.1

Type RM Length L Ch R = 1,12613,548,548,548
BEGIN DESCRIPTION:
SANDY 10 25.0
END DESCRIPTION:
XS GIS Cut Line= 3
      2797814.35     10152998.69      2798306.14     10153354.40
      2798622.15     10153337.77
#Sta/Elev= 30
  4524.8 1317.24  4546.8 1317.73  4557.6 1319.34  4563.8 1318.59  4572.3 1320.31
  4578.5 1318.94  4622.6 1319.56  4628.8 1318.89  4643.5 1319.58  4649.9 1321.18
  4693.8 1315.44  4699.9 1312.70  4708.5 1311.10  4714.6 1310.50  4723.2 1311.10
  4744.0 1307.85  4752.3 1307.63  4785.8 1304.50  4809.0 1304.01  4815.2 1301.76
  4836.1 1299.48  4945.1 1292.71  4966.0 1290.62  4999.1 1289.42  4999.4 1286.42
  5003.7 1286.42  5004.1 1289.42  5044.8 1292.89  5241.4 1301.44  5448.2 1312.38
#Mann=5,-1,0
  4524.8    0.05       0  4546.8    0.12       0  4752.3    0.05       0
  4999.1    0.05       0  5004.1    0.05       0
Bank Sta=4999.1,5004.1
Exp/Cntr=0.3,0.1

Type RM Length L Ch R = 1,12065,481,481,481
BEGIN DESCRIPTION:
SANDY 10 24.0
END DESCRIPTION:
XS GIS Cut Line= 3
      2797441.99     10153705.31      2798024.46     10153683.83
      2798625.98     10153471.38
#Sta/Elev= 30
  4552.9 1319.14  4696.7 1309.12  4796.8 1300.88  4816.8 1298.63  4886.8 1295.03
  4916.8 1291.91  4965.5 1284.52  4976.9 1283.10  4984.3 1281.21  4984.7 1278.21
  4989.0 1278.21  4989.4 1281.21  5006.9 1282.43  5015.7 1282.17  5020.7 1282.74
  5026.9 1284.84  5046.9 1287.46  5077.0 1286.50  5117.0 1286.89  5147.6 1285.70
  5209.5 1286.23  5221.9 1285.33  5232.5 1286.62  5240.4 1285.87  5271.7 1286.84
  5389.7 1289.19  5497.6 1293.15  5582.5 1297.29  5731.0 1306.08  5773.7 1307.39
#Mann=5,-1,0
  4552.9    0.05       0  4965.5    0.12       0  4984.3    0.07       0
  4989.4    0.12       0  5271.7    0.05       0
Bank Sta=4984.3,4989.4
Exp/Cntr=0.3,0.1

Type RM Length L Ch R = 1,11584,263,263,263
BEGIN DESCRIPTION:
SANDY 10 23.0
END DESCRIPTION:
XS GIS Cut Line= 3
      2797711.73     10154041.90      2798275.36     10153984.40
      2798728.69     10153941.64
#Sta/Elev= 30
  4503.4 1309.19  4597.8 1302.27  4668.2 1299.17  4698.4 1296.56  4768.7 1292.44
  4788.8 1290.43  4829.0 1288.06  4859.2 1284.82  4934.7 1278.88  4949.7 1278.84
  4979.8 1277.22  5010.0 1275.07  5017.3 1273.68  5017.7 1270.68  5022.3 1270.68
  5022.7 1273.68  5029.2 1275.36  5034.2 1273.99  5040.1 1277.87  5050.2 1279.75
  5080.3 1280.28  5130.5 1283.69  5244.7 1286.90  5331.4 1291.81  5348.2 1293.79
  5353.2 1293.46  5401.7 1296.86  5456.7 1299.80  5512.2 1304.44  5525.3 1305.00
#Mann=3,-1,0
  4503.4    0.05       0  5017.3    0.03       0  5022.7    0.05       0
Bank Sta=5017.3,5022.7
Exp/Cntr=0.3,0.1

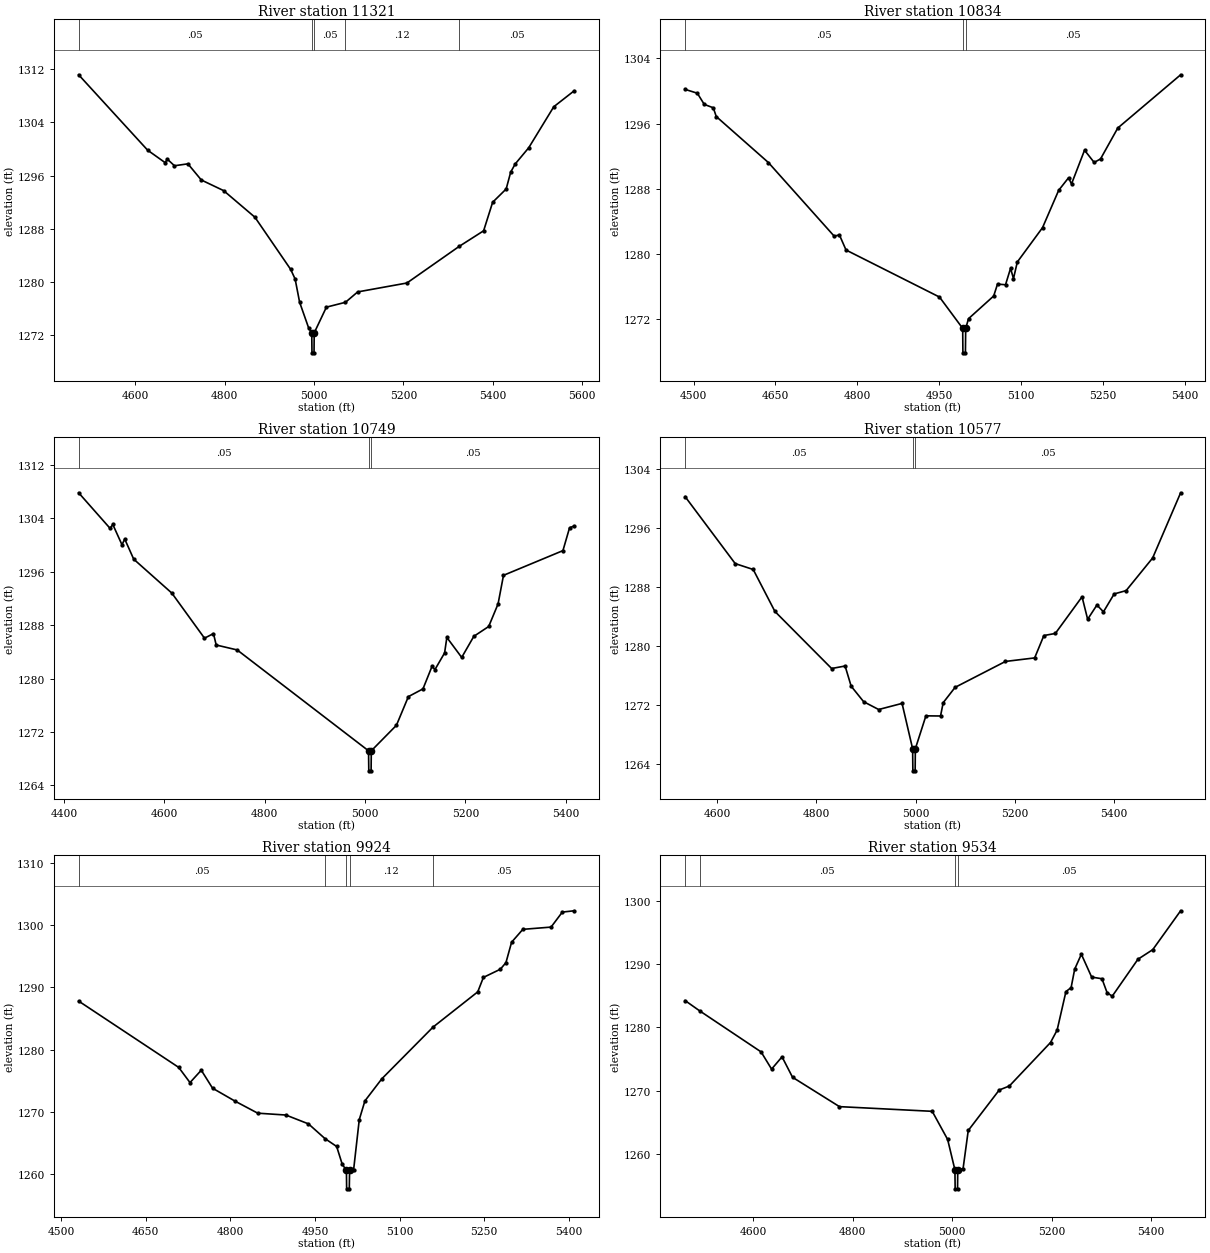
Type RM Length L Ch R = 1,11321,487,487,487
BEGIN DESCRIPTION:
SANDY 10 22.0
END DESCRIPTION:
XS GIS Cut Line= 3
      2797671.16     10154244.81      2798384.92     10154256.74
      2798776.43     10154201.83
#Sta/Elev= 30
  4472.9 1311.16  4627.4 1299.82  4666.5 1297.95  4671.5 1298.47  4687.4 1297.48
  4717.5 1297.77  4747.5 1295.34  4797.5 1293.74  4867.5 1289.74  4947.5 1281.90
  4957.5 1280.45  4967.5 1276.97  4987.5 1273.14  4994.7 1272.35  4995.2 1269.35
  4999.8 1269.35  5000.2 1272.35  5027.5 1276.22  5070.2 1276.95  5097.5 1278.51
  5207.7 1279.85  5324.8 1285.36  5379.4 1287.70  5399.6 1291.99  5429.9 1293.99
  5440.0 1296.52  5450.1 1297.75  5480.4 1300.19  5536.4 1306.35  5582.1 1308.75
#Mann=5,-1,0
  4472.9    0.05       0  4994.7    0.05       0  5000.2    0.05       0
  5070.2    0.12       0  5324.8    0.05       0
Bank Sta=4994.7,5000.2
Exp/Cntr=0.3,0.1

Type RM Length L Ch R = 1,10834,85,85,85
BEGIN DESCRIPTION:
Mapping XS 3a2dfe98
END DESCRIPTION:
XS GIS Cut Line= 2
      2797943.29     10154438.17      2798782.10     10154786.08
#Sta/Elev= 30
  4484.6 1300.19  4507.0 1299.72  4519.7 1298.35  4536.3 1297.93  4541.7 1296.86
  4637.2 1291.22  4757.8 1282.19  4767.4 1282.34  4779.5 1280.49  4950.8 1274.72
  4993.3 1270.88  4993.7 1267.88  4998.3 1267.88  4998.8 1270.88  5004.0 1272.07
  5050.1 1274.85  5057.1 1276.31  5071.8 1276.23  5081.0 1278.24  5086.4 1276.99
  5093.4 1279.02  5139.6 1283.23  5169.2 1287.81  5187.3 1289.35  5192.7 1288.59
  5216.6 1292.73  5234.2 1291.23  5245.9 1291.66  5277.5 1295.45  5392.7 1301.98
#Mann=3,-1,0
  4484.6    0.05       0  4993.3    0.03       0  4998.8    0.05       0
Bank Sta=4993.3,4998.8
Exp/Cntr=0.3,0.1

Type RM Length L Ch R = 1,10749,172,172,172
BEGIN DESCRIPTION:
SANDY 10 21.0
END DESCRIPTION:
XS GIS Cut Line= 3
      2797864.51     10154493.07      2798532.92     10154774.75
      2798776.44     10154872.64
#Sta/Elev= 30
  4429.1 1307.81  4491.8 1302.48  4497.2 1303.07  4515.5 1300.03  4521.0 1300.88
  4538.9 1297.87  4614.9 1292.79  4680.0 1286.04  4697.9 1286.73  4703.3 1285.02
  4745.1 1284.28  5007.0 1269.18  5007.5 1266.18  5012.1 1266.18  5012.5 1269.18
  5062.6 1273.00  5086.4 1277.29  5115.5 1278.45  5133.8 1281.87  5139.2 1281.32
  5158.6 1283.83  5163.1 1286.15  5192.7 1283.16  5216.9 1286.32  5246.5 1287.79
  5265.2 1291.17  5276.0 1295.45  5394.5 1299.15  5407.7 1302.57  5416.9 1302.84
#Mann=3,-1,0
  4429.1    0.05       0  5007.0    0.03       0  5012.5    0.05       0
Bank Sta=5007,5012.5
Exp/Cntr=0.3,0.1

Type RM Length L Ch R = 1,10577,653,653,653
BEGIN DESCRIPTION:
SANDY 10 20.0
END DESCRIPTION:
XS GIS Cut Line= 3
      2797866.93     10154748.50      2798197.50     10154821.16
      2798809.82     10155070.76
#Sta/Elev= 30
  4535.0 1300.29  4636.1 1291.19  4672.4 1290.39  4716.2 1284.69  4830.6 1276.94
  4857.8 1277.28  4870.0 1274.54  4895.2 1272.43  4925.5 1271.37  4972.7 1272.20
  4994.0 1266.04  4994.5 1263.04  4999.1 1263.04  4999.5 1266.04  5020.8 1270.51
  5050.3 1270.49  5055.7 1272.30  5079.7 1274.38  5181.3 1277.90  5240.2 1278.38
  5258.8 1281.42  5281.9 1281.70  5335.8 1286.68  5347.1 1283.63  5365.8 1285.56
  5379.0 1284.64  5400.6 1287.07  5424.7 1287.52  5478.2 1291.95  5534.7 1300.81
#Mann=3,-1,0
  4535.0    0.05       0  4994.0    0.03       0  4999.5    0.05       0
Bank Sta=4994,4999.5
Exp/Cntr=0.3,0.1

Type RM Length L Ch R = 1,9924,390,390,390
BEGIN DESCRIPTION:
Mapping XS b8e0cde2
END DESCRIPTION:
XS GIS Cut Line= 2
      2797998.24     10155316.64      2798876.65     10155290.38
#Sta/Elev= 30
  4530.9 1287.79  4708.4 1277.14  4728.4 1274.70  4748.4 1276.69  4768.4 1273.80
  4808.5 1271.71  4848.5 1269.79  4898.5 1269.49  4938.5 1268.07  4967.6 1265.72
  4988.5 1264.44  4998.5 1261.55  5005.8 1260.64  5006.2 1257.64  5010.9 1257.64
  5011.4 1260.64  5018.6 1260.73  5028.6 1268.76  5038.6 1271.76  5068.6 1275.31
  5159.4 1283.61  5238.7 1289.27  5248.7 1291.59  5278.7 1292.90  5288.7 1293.96
  5298.7 1297.24  5318.7 1299.31  5368.7 1299.67  5388.7 1302.08  5409.7 1302.29
#Mann=5,-1,0
  4530.9    0.05       0  4967.6    0.12       0  5005.8    0.07       0
  5011.4    0.12       0  5159.4    0.05       0
Bank Sta=5005.8,5011.4
Exp/Cntr=0.3,0.1

Type RM Length L Ch R = 1,9534,387,387,387
BEGIN DESCRIPTION:
SANDY 10 19.0
END DESCRIPTION:
XS GIS Cut Line= 3
      2798036.39     10155412.13      2798425.50     10155667.55
      2798938.72     10155801.23
#Sta/Elev= 30
  4463.5 1284.24  4492.7 1282.62  4616.2 1276.13  4637.3 1273.41  4658.3 1275.35
  4679.4 1272.12  4773.7 1267.48  4960.1 1266.74  4991.1 1262.29  5005.7 1257.49
  5006.2 1254.49  5011.0 1254.49  5011.4 1257.49  5022.1 1257.68  5032.5 1263.71
  5094.8 1270.11  5115.1 1270.74  5197.8 1277.61  5211.1 1279.57  5228.8 1285.66
  5239.2 1286.29  5246.4 1289.21  5259.8 1291.56  5280.5 1287.95  5301.2 1287.69
  5311.5 1285.49  5321.8 1284.93  5373.5 1290.77  5403.3 1292.29  5459.3 1298.43
#Mann=4,-1,0
  4463.5    0.12       0  4492.7    0.05       0  5005.7    0.05       0
  5011.4    0.05       0
Bank Sta=5005.7,5011.4
Exp/Cntr=0.3,0.1

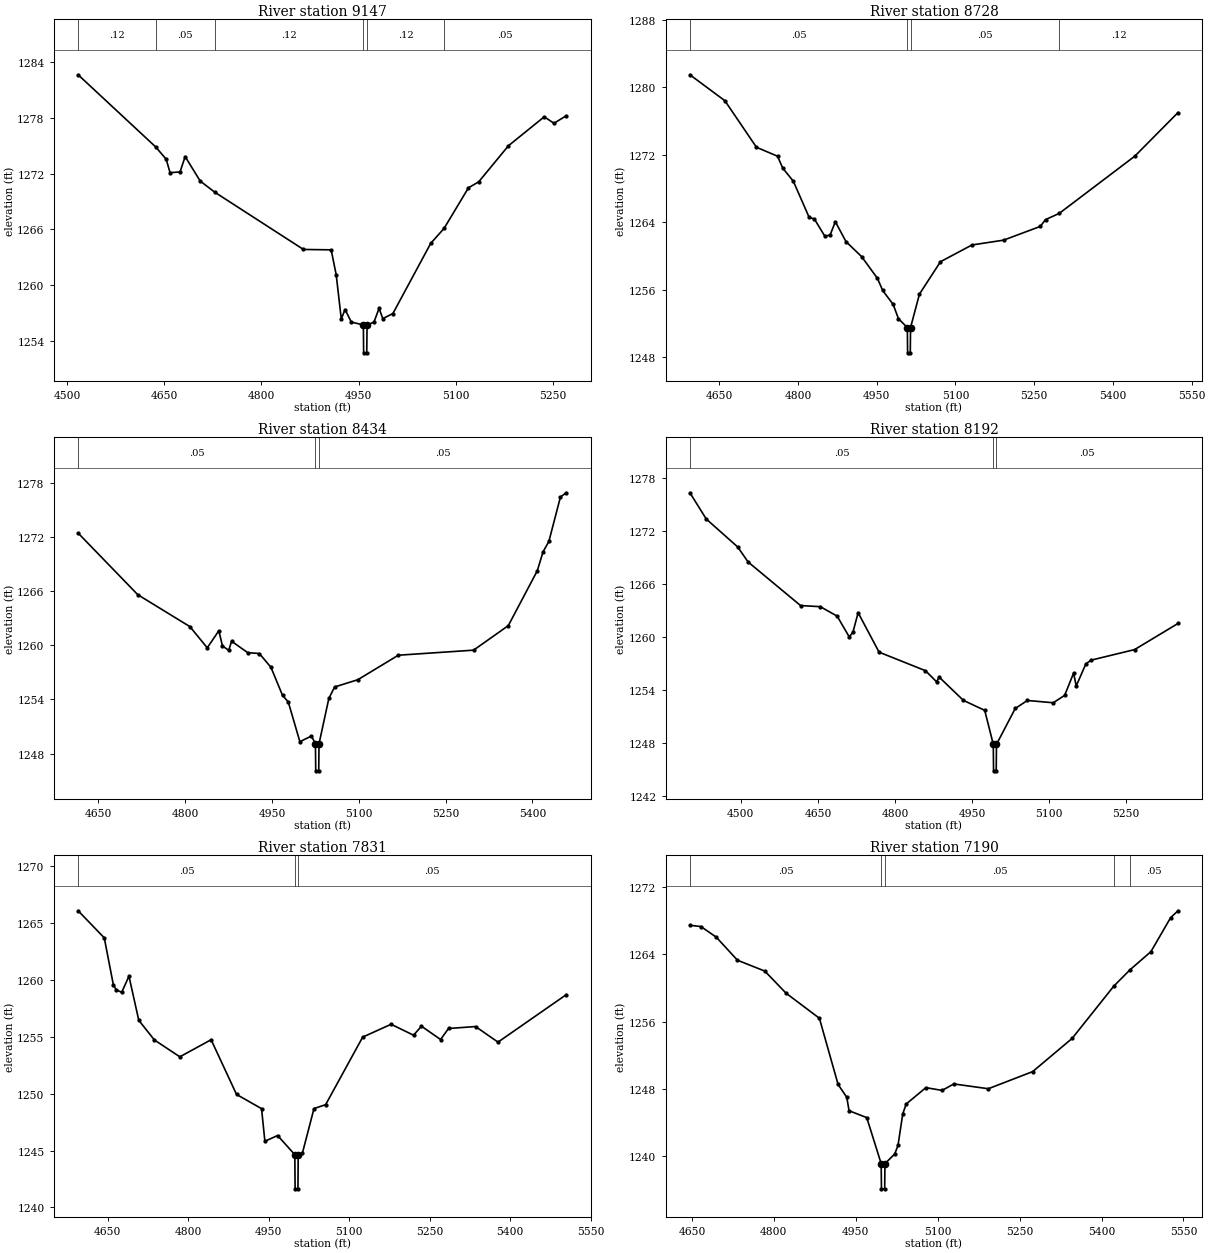
Type RM Length L Ch R = 1,9147,419,419,419
BEGIN DESCRIPTION:
SANDY 10 18.0
END DESCRIPTION:
XS GIS Cut Line= 3
      2797940.93     10155481.39      2798251.23     10155999.36
      2798399.27     10156020.85
#Sta/Elev= 30
  4517.1 1282.64  4636.8 1274.88  4653.0 1273.56  4659.0 1272.11  4674.4 1272.19
  4682.3 1273.84  4705.5 1271.21  4728.0 1270.01  4864.9 1263.85  4907.7 1263.81
  4915.5 1261.11  4923.3 1256.37  4929.1 1257.39  4938.8 1256.04  4957.4 1255.73
  4957.8 1252.73  4962.6 1252.73  4963.1 1255.73  4973.7 1256.03  4981.6 1257.51
  4987.4 1256.41  5003.0 1256.96  5061.3 1264.50  5082.0 1266.12  5119.6 1270.48
  5135.5 1271.13  5181.4 1275.01  5236.6 1278.12  5251.6 1277.42  5270.5 1278.23
#Mann=6,-1,0
  4517.1    0.12       0  4636.8    0.05       0  4728.0    0.12       0
  4957.4    0.07       0  4963.1    0.12       0  5082.0    0.05       0
Bank Sta=4957.4,4963.1
Exp/Cntr=0.3,0.1

Type RM Length L Ch R = 1,8728,294,294,294
BEGIN DESCRIPTION:
SANDY 10 17.0
END DESCRIPTION:
XS GIS Cut Line= 3
      2797802.45     10155526.73      2797783.35     10155772.58
      2797757.10     10156455.29
#Sta/Elev= 30
  4594.2 1281.51  4660.8 1278.43  4721.0 1272.90  4761.1 1271.84  4771.1 1270.42
  4791.2 1268.87  4821.3 1264.58  4831.3 1264.38  4851.3 1262.33  4861.3 1262.49
  4871.3 1264.06  4891.4 1261.71  4921.4 1259.91  4951.4 1257.34  4961.4 1255.90
  4981.4 1254.24  4991.4 1252.55  5008.4 1251.49  5008.9 1248.49  5014.0 1248.49
  5014.5 1251.49  5031.5 1255.47  5071.5 1259.31  5131.5 1261.30  5191.6 1261.87
  5261.6 1263.50  5271.6 1264.31  5297.8 1265.05  5441.8 1271.85  5524.0 1277.02
#Mann=4,-1,0
  4594.2    0.05       0  5008.4    0.05       0  5014.5    0.05       0
  5297.8    0.12       0
Bank Sta=5008.4,5014.5
Exp/Cntr=0.3,0.1

Type RM Length L Ch R = 1,8434,242,242,242
BEGIN DESCRIPTION:
SANDY 10 16.0
END DESCRIPTION:
XS GIS Cut Line= 3
      2797473.02     10155510.03      2797480.18     10155760.65
      2797505.68     10156353.08
#Sta/Elev= 30
  4614.8 1272.44  4717.9 1265.61  4808.0 1262.07  4838.0 1259.72  4858.0 1261.61
  4864.3 1259.93  4875.1 1259.44  4880.1 1260.45  4908.0 1259.18  4928.0 1259.09
  4948.1 1257.56  4968.1 1254.45  4978.1 1253.71  4998.1 1249.31  5018.1 1249.94
  5025.0 1249.08  5025.5 1246.08  5030.7 1246.08  5031.2 1249.08  5048.2 1254.11
  5058.2 1255.38  5098.2 1256.18  5168.3 1258.90  5298.4 1259.46  5358.4 1262.18
  5408.5 1268.26  5418.5 1270.37  5428.5 1271.51  5448.5 1276.44  5458.5 1276.91
#Mann=3,-1,0
  4614.8    0.05       0  5025.0    0.05       0  5031.2    0.05       0
Bank Sta=5025,5031.2
Exp/Cntr=0.3,0.1

Type RM Length L Ch R = 1,8192,361,361,361
BEGIN DESCRIPTION:
SANDY 10 15.0
END DESCRIPTION:
XS GIS Cut Line= 3
      2797310.70     10155361.96      2797218.14     10155828.03
      2797344.12     10156285.84
#Sta/Elev= 30
  4400.9 1276.32  4432.7 1273.35  4493.8 1270.19  4514.2 1268.48  4616.2 1263.55
  4654.8 1263.42  4687.5 1262.35  4711.0 1260.00  4718.1 1260.51  4728.3 1262.74
  4769.1 1258.27  4859.4 1256.17  4880.9 1254.92  4886.1 1255.44  4933.2 1252.81
  4974.7 1251.68  4991.4 1247.83  4991.9 1244.83  4997.1 1244.83  4997.6 1247.83
  5034.1 1251.89  5057.7 1252.80  5108.1 1252.54  5130.3 1253.38  5147.7 1255.90
  5152.8 1254.44  5171.7 1256.96  5182.1 1257.37  5266.4 1258.56  5350.9 1261.52
#Mann=3,-1,0
  4400.9    0.05       0  4991.4    0.05       0  4997.6    0.05       0
Bank Sta=4991.4,4997.6
Exp/Cntr=0.3,0.1

Type RM Length L Ch R = 1,7831,641,641,641
BEGIN DESCRIPTION:
Mapping XS 52c8398a
END DESCRIPTION:
XS GIS Cut Line= 3
      2796744.93     10155598.28      2796959.79     10156106.79
      2797250.83     10156314.33
#Sta/Elev= 30
  4595.2 1266.09  4643.9 1263.71  4660.8 1259.59  4666.2 1259.14  4676.4 1258.92
  4689.9 1260.34  4708.2 1256.46  4737.3 1254.73  4784.7 1253.25  4843.0 1254.75
  4890.4 1249.94  4937.0 1248.69  4943.2 1245.82  4966.9 1246.33  4999.0 1244.64
  4999.5 1241.64  5004.8 1241.64  5005.3 1244.64  5013.0 1244.76  5034.7 1248.70
  5056.4 1249.04  5125.4 1254.98  5178.4 1256.11  5220.2 1255.15  5235.0 1255.94
  5270.6 1254.77  5285.4 1255.74  5335.8 1255.91  5377.6 1254.54  5504.7 1258.71
#Mann=3,-1,0
  4595.2    0.05       0  4999.0    0.05       0  5005.3    0.05       0
Bank Sta=4999,5005.3
Exp/Cntr=0.3,0.1

Type RM Length L Ch R = 1,7190,298,298,298
BEGIN DESCRIPTION:
SANDY 10 14.0
END DESCRIPTION:
XS GIS Cut Line= 3
      2796343.91     10156288.21      2796606.49     10156421.89
      2797105.65     10156753.09
#Sta/Elev= 30
  4646.3 1267.47  4666.6 1267.32  4694.5 1266.06  4733.4 1263.31  4783.4 1262.02
  4822.3 1259.39  4883.4 1256.40  4917.6 1248.52  4933.5 1246.99  4937.7 1245.39
  4970.1 1244.57  4996.5 1239.09  4997.0 1236.09  5002.9 1236.09  5003.4 1239.09
  5021.3 1240.24  5027.3 1241.26  5036.0 1245.01  5042.3 1246.19  5078.4 1248.14
  5108.0 1247.81  5129.5 1248.58  5192.7 1248.01  5273.9 1250.05  5346.1 1254.00
  5422.5 1260.23  5452.4 1262.19  5490.4 1264.33  5526.5 1268.38  5540.0 1269.20
#Mann=5,-1,0
  4646.3    0.05       0  4996.5    0.03       0  5003.4    0.05       0
  5422.5    0.12       0  5452.4    0.05       0
Bank Sta=4996.5,5003.4
Exp/Cntr=0.3,0.1

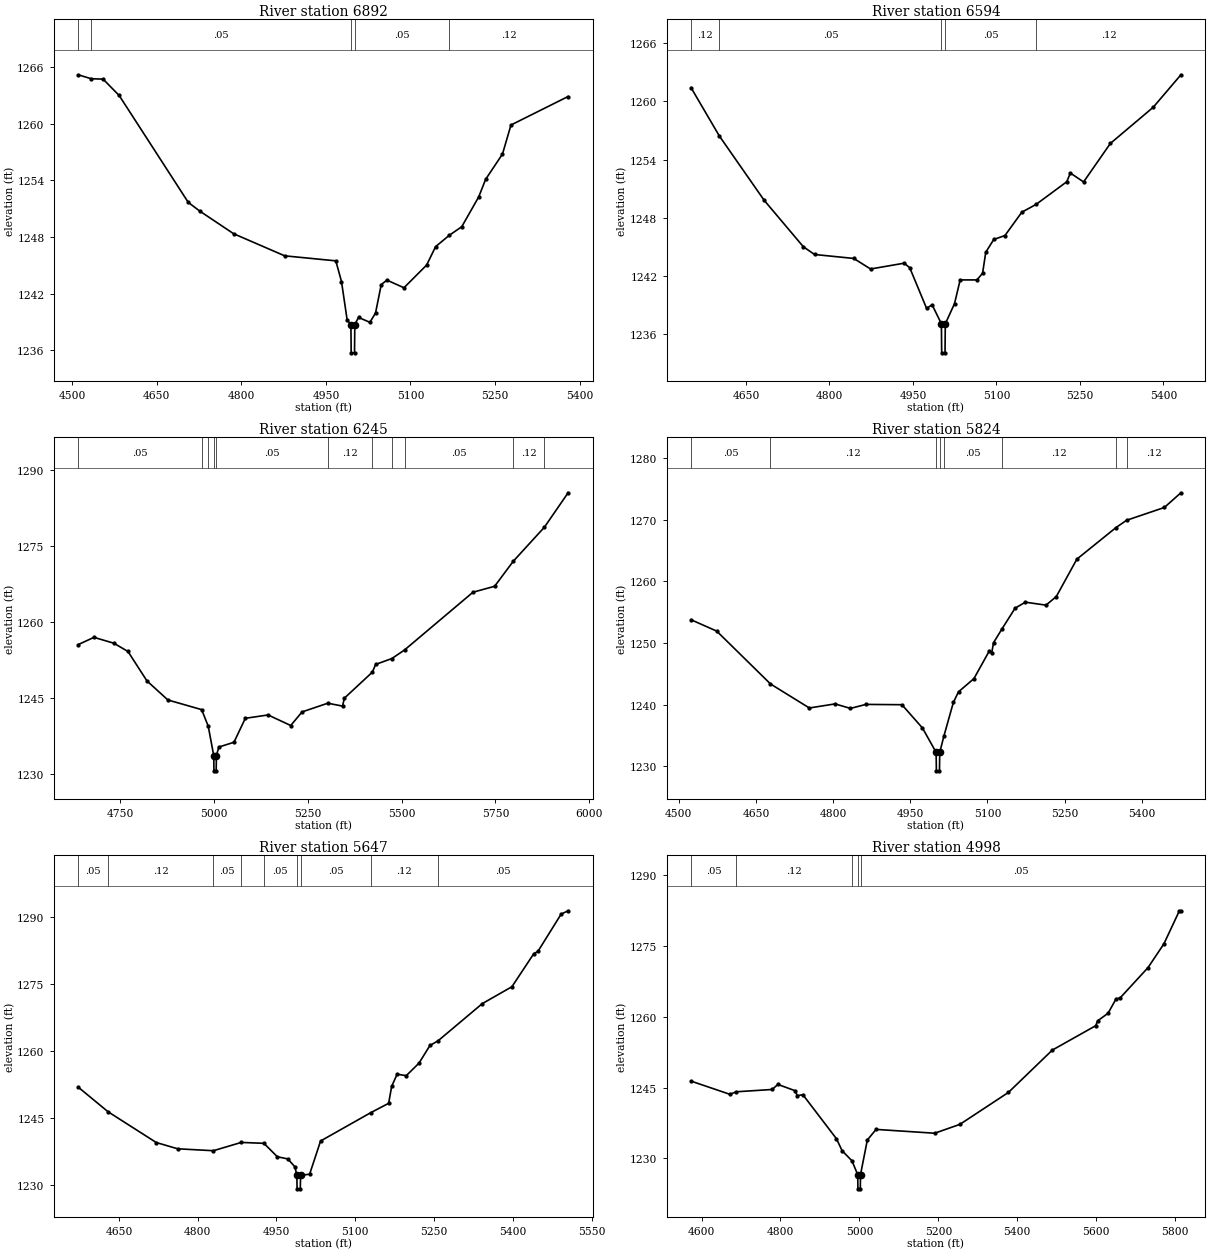
Type RM Length L Ch R = 1,6892,298,298,298
BEGIN DESCRIPTION:
SANDY 10 13.0
END DESCRIPTION:
XS GIS Cut Line= 3
      2796121.86     10156689.25      2796752.10     10156763.25
      2796947.89     10156892.19
#Sta/Elev= 30
  4510.6 1265.17  4533.7 1264.75  4554.7 1264.71  4583.2 1262.98  4705.8 1251.66
  4725.9 1250.75  4786.3 1248.34  4876.9 1246.00  4967.5 1245.47  4977.6 1243.28
  4987.7 1239.19  4994.3 1238.73  4994.8 1235.73  5000.7 1235.73  5001.2 1238.73
  5007.8 1239.48  5028.0 1238.96  5038.0 1239.95  5048.1 1242.95  5058.2 1243.43
  5088.4 1242.62  5128.6 1245.02  5144.5 1246.97  5168.9 1248.18  5190.9 1249.08
  5221.0 1252.24  5233.3 1254.10  5263.2 1256.78  5278.2 1259.85  5379.6 1262.87
#Mann=5,-1,0
  4510.6    0.12       0  4533.7    0.05       0  4994.3    0.03       0
  5001.2    0.05       0  5168.9    0.12       0
Bank Sta=4994.3,5001.2
Exp/Cntr=0.3,0.1

Type RM Length L Ch R = 1,6594,349,349,349
BEGIN DESCRIPTION:
SANDY 10 12.0
END DESCRIPTION:
XS GIS Cut Line= 3
      2796105.23     10156987.65      2796670.75     10157052.56
      2796978.90     10157095.07
#Sta/Elev= 30
  4551.2 1261.43  4602.1 1256.43  4682.5 1249.79  4753.0 1244.98  4773.1 1244.18
  4843.6 1243.77  4873.8 1242.68  4934.2 1243.28  4944.2 1242.81  4974.4 1238.62
  4984.5 1238.97  5001.1 1237.01  5001.6 1234.01  5007.6 1234.01  5008.1 1237.01
  5024.7 1239.10  5034.8 1241.55  5065.0 1241.55  5075.1 1242.24  5080.8 1244.41
  5095.2 1245.73  5115.3 1246.14  5145.6 1248.55  5171.3 1249.36  5226.4 1251.70
  5232.8 1252.60  5256.6 1251.68  5304.7 1255.66  5381.7 1259.40  5431.5 1262.76
#Mann=5,-1,0
  4551.2    0.12       0  4602.1    0.05       0  5001.1    0.03       0
  5008.1    0.05       0  5171.3    0.12       0
Bank Sta=5001.1,5008.1
Exp/Cntr=0.3,0.1

Type RM Length L Ch R = 1,6245,421,421,421
BEGIN DESCRIPTION:
Mapping XS c538955f
END DESCRIPTION:
XS GIS Cut Line= 3
      2796074.18     10157400.62      2796596.94     10157329.01
      2797370.40     10157238.29
#Sta/Elev= 30
  4637.4 1255.62  4679.3 1257.05  4732.2 1255.90  4770.1 1254.26  4820.6 1248.46
  4876.5 1244.69  4966.6 1242.78  4984.1 1239.51  4998.8 1233.70  4999.3 1230.70
  5005.3 1230.70  5005.8 1233.70  5012.4 1235.40  5052.7 1236.34  5083.0 1241.07
  5143.6 1241.73  5204.1 1239.65  5234.3 1242.33  5303.0 1244.05  5342.2 1243.48
  5347.2 1245.05  5421.8 1250.18  5430.4 1251.70  5473.8 1252.87  5507.6 1254.56
  5690.1 1265.96  5747.8 1267.13  5797.4 1272.06  5880.5 1278.79  5943.8 1285.59
#Mann=11,-1,0
  4637.4    0.05       0  4966.6    0.12       0  4984.1    0.05       0
  4998.8    0.03       0  5005.8    0.05       0  5303.0    0.12       0
  5421.8    0.05       0  5473.8    0.12       0  5507.6    0.05       0
  5797.4    0.12       0  5880.5    0.05       0
Bank Sta=4998.8,5005.8
Exp/Cntr=0.3,0.1

Type RM Length L Ch R = 1,5824,177,177,177
BEGIN DESCRIPTION:
SANDY 10 11.0
END DESCRIPTION:
XS GIS Cut Line= 3
      2796205.68     10157603.11      2796796.83     10157608.17
      2797157.93     10157617.85
#Sta/Elev= 30
  4523.8 1253.77  4573.8 1251.92  4678.3 1243.34  4753.8 1239.44  4803.8 1240.10
  4833.8 1239.37  4863.8 1240.02  4933.8 1239.97  4973.8 1236.18  5000.3 1232.23
  5000.8 1229.23  5006.8 1229.23  5007.3 1232.23  5015.6 1234.93  5033.8 1240.34
  5043.8 1242.06  5073.8 1244.21  5103.4 1248.66  5108.4 1248.40  5111.9 1250.04
  5127.8 1252.21  5153.8 1255.65  5173.8 1256.62  5213.9 1256.14  5233.9 1257.53
  5273.9 1263.61  5350.0 1268.74  5370.5 1269.92  5443.9 1272.00  5476.2 1274.39
#Mann=8,-1,0
  4523.8    0.05       0  4678.3    0.12       0  5000.3    0.07       0
  5007.3    0.12       0  5015.6    0.05       0  5127.8    0.12       0
  5350.0    0.05       0  5370.5    0.12       0
Bank Sta=5000.3,5007.3
Exp/Cntr=0.3,0.1

Type RM Length L Ch R = 1,5647,649,649,649
BEGIN DESCRIPTION:
SANDY 10 10.0
END DESCRIPTION:
XS GIS Cut Line= 3
      2796255.67     10157653.11      2796563.52     10157753.92
      2797148.42     10157923.42
#Sta/Elev= 30
  4572.5 1251.88  4629.4 1246.35  4721.1 1239.45  4761.9 1238.04  4829.8 1237.61
  4883.0 1239.47  4926.1 1239.27  4951.7 1236.25  4971.6 1235.77  4985.3 1233.97
  4988.8 1232.05  4989.3 1229.05  4995.4 1229.05  4995.9 1232.05  5013.2 1232.35
  5034.0 1239.79  5129.1 1246.12  5163.6 1248.25  5169.4 1252.06  5179.8 1254.79
  5197.2 1254.46  5221.4 1257.27  5242.3 1261.24  5257.7 1262.28  5341.9 1270.63
  5398.4 1274.43  5440.1 1281.86  5447.8 1282.34  5492.1 1290.73  5505.4 1291.48
#Mann=9,-1,0
  4572.5    0.05       0  4629.4    0.12       0  4829.8    0.05       0
  4883.0    0.12       0  4926.1    0.05       0  4988.8    0.05       0
  4995.9    0.05       0  5129.1    0.12       0  5257.7    0.05       0
Bank Sta=4988.8,4995.9
Exp/Cntr=0.3,0.1

Type RM Length L Ch R = 1,4998,1083,1083,1083
BEGIN DESCRIPTION:
SANDY 10 9.0
END DESCRIPTION:
XS GIS Cut Line= 3
      2795911.82     10157677.53      2796451.67     10158121.72
      2796988.39     10158197.93
#Sta/Elev= 30
  4573.4 1246.37  4672.1 1243.57  4687.7 1244.11  4779.0 1244.60  4793.4 1245.67
  4836.4 1244.36  4842.9 1243.30  4856.8 1243.49  4941.9 1234.17  4956.2 1231.63
  4981.1 1229.51  4995.7 1226.57  4996.2 1223.57  5002.3 1223.57  5002.8 1226.57
  5020.1 1233.91  5042.3 1236.15  5190.8 1235.34  5254.7 1237.22  5377.6 1243.98
  5488.7 1252.93  5598.6 1258.09  5603.7 1259.13  5630.1 1260.74  5650.3 1263.78
  5660.4 1263.96  5731.1 1270.38  5771.5 1275.42  5810.7 1282.42  5814.6 1282.42
#Mann=5,-1,0
  4573.4    0.05       0  4687.7    0.12       0  4981.1    0.05       0
  4995.7    0.05       0  5002.8    0.05       0
Bank Sta=4995.7,5002.8
Exp/Cntr=0.3,0.1