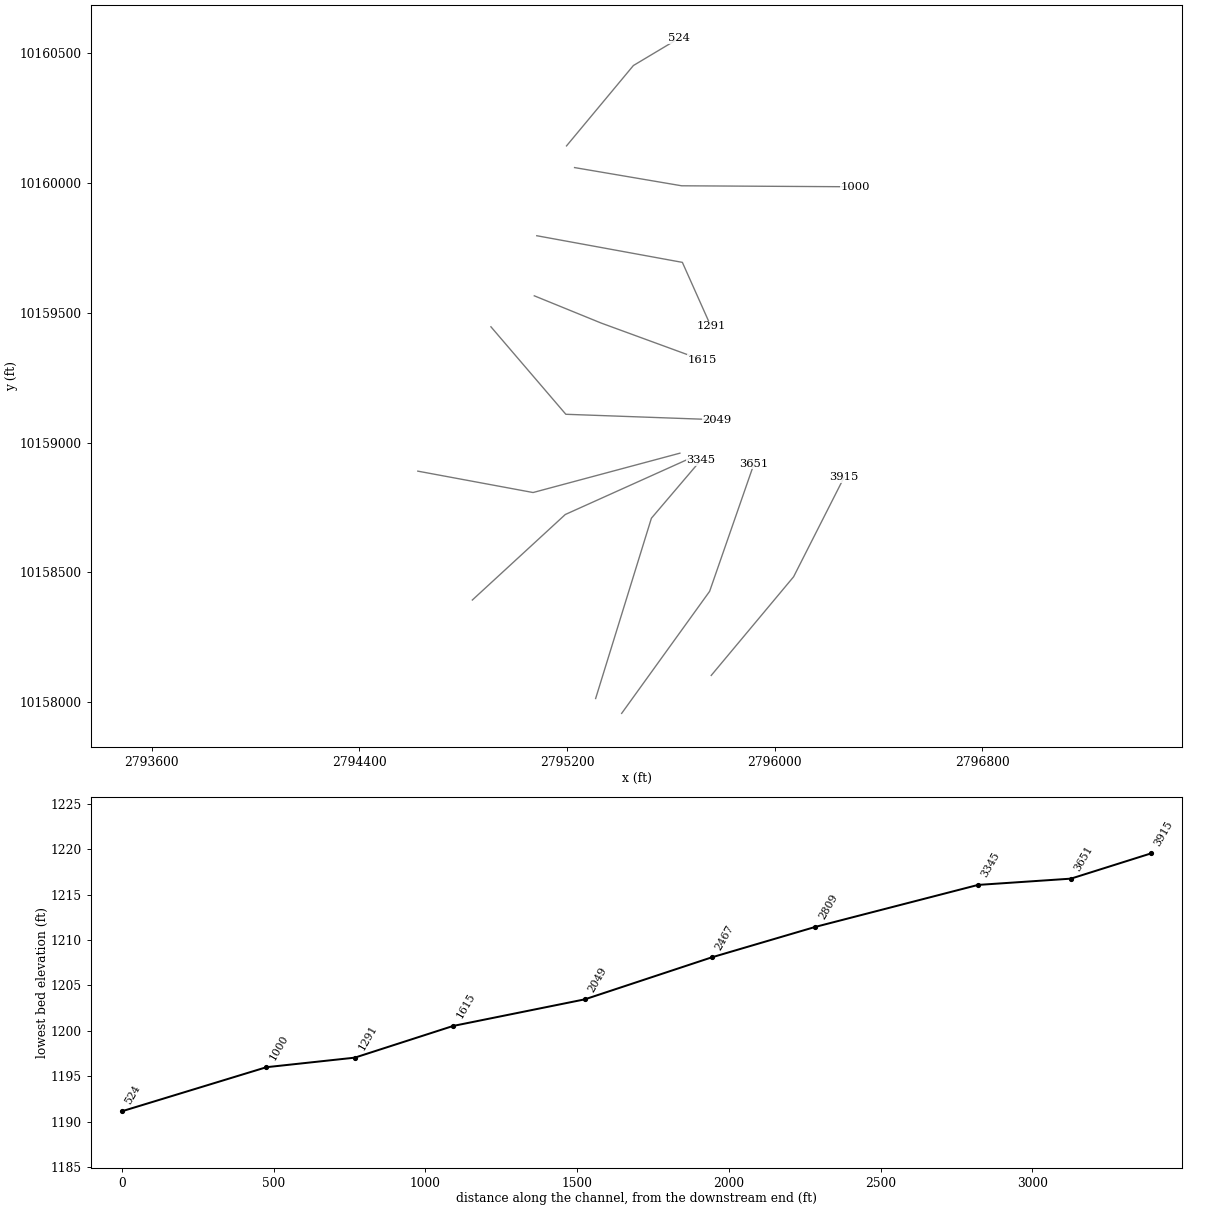
HEC-RAS study SANDY 10.prj: SANDY 10 Base Level Engineering

--- SANDY 10.g01 (geometry) --- (continued)

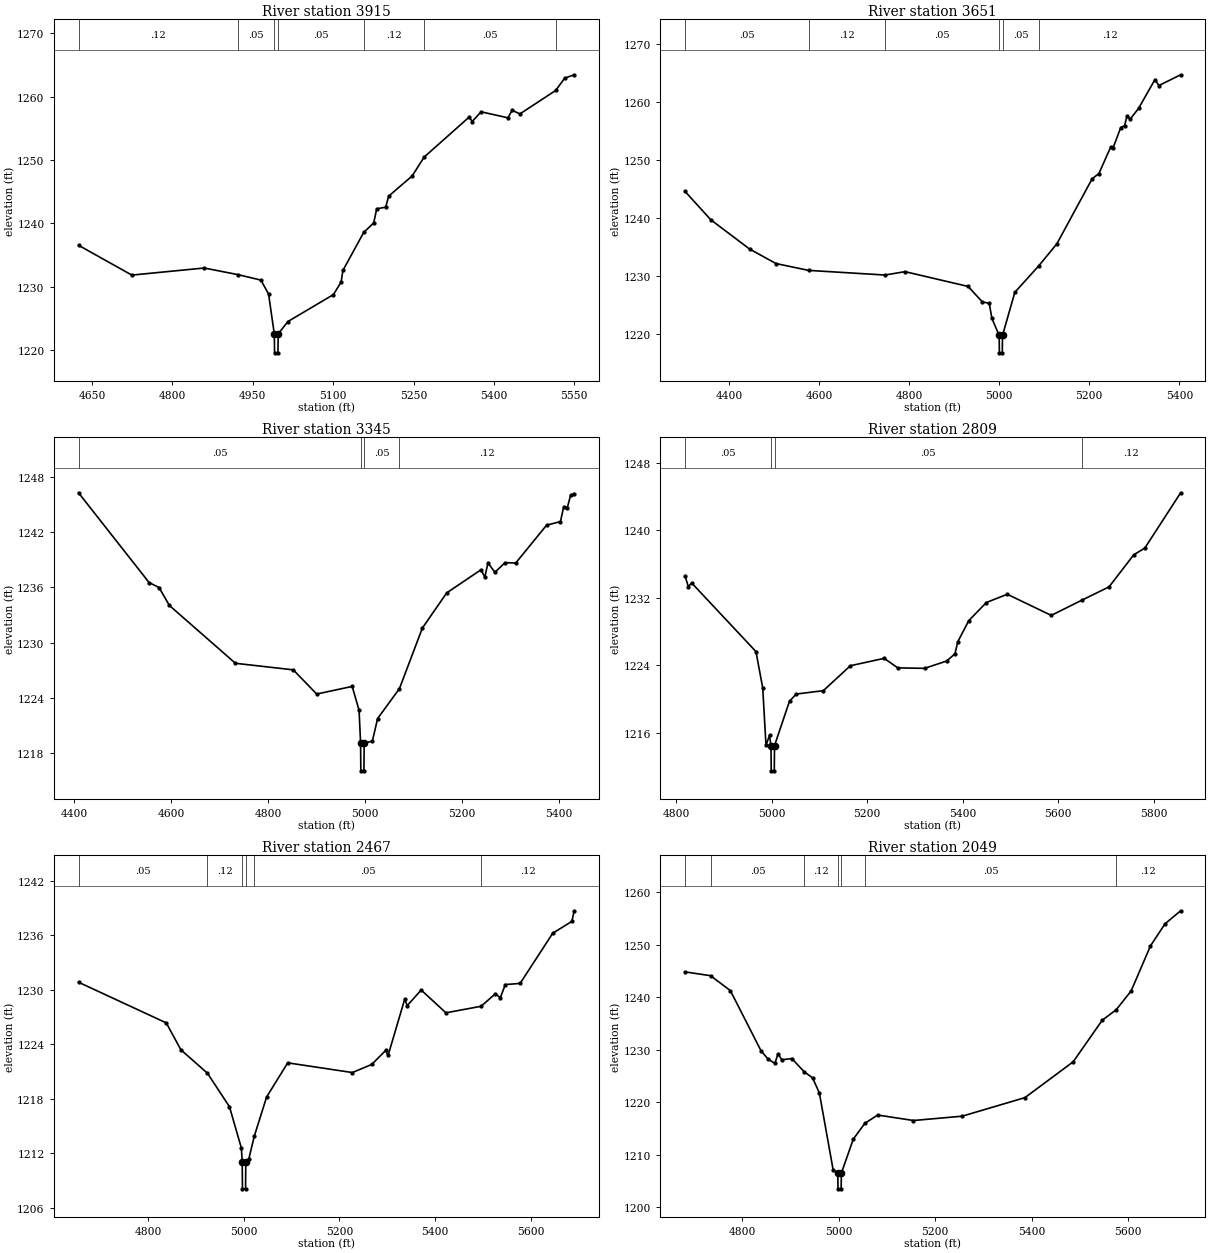
Type RM Length L Ch R = 1,3915,264,264,264
BEGIN DESCRIPTION:
SANDY 10 8.0
END DESCRIPTION:
XS GIS Cut Line= 3
      2795755.71     10158103.14      2796073.11     10158483.26
      2796267.52     10158866.35
#Sta/Elev= 30
  4624.9 1236.53  4724.4 1231.82  4859.4 1232.94  4922.0 1231.90  4965.2 1231.03
  4979.5 1228.83  4990.2 1222.54  4990.7 1219.54  4997.0 1219.54  4997.5 1222.54
  5015.7 1224.49  5100.5 1228.74  5114.9 1230.72  5118.2 1232.55  5157.1 1238.57
  5175.7 1240.06  5181.3 1242.29  5198.0 1242.55  5203.6 1244.29  5247.3 1247.47
  5269.8 1250.46  5353.8 1256.78  5359.4 1256.08  5376.1 1257.61  5426.2 1256.66
  5433.9 1257.85  5448.5 1257.28  5515.2 1260.98  5531.9 1262.92  5549.7 1263.46
#Mann=7,-1,0
  4624.9    0.12       0  4922.0    0.05       0  4990.2    0.05       0
  4997.5    0.05       0  5157.1    0.12       0  5269.8    0.05       0
  5515.2    0.12       0
Bank Sta=4990.2,4997.5
Exp/Cntr=0.3,0.1

Type RM Length L Ch R = 1,3651,306,306,306
BEGIN DESCRIPTION:
SANDY 10 7.0
END DESCRIPTION:
XS GIS Cut Line= 3
      2795410.54     10157956.85      2795749.50     10158427.10
      2795920.50     10158918.73
#Sta/Elev= 30
  4302.6 1244.63  4360.0 1239.72  4445.9 1234.68  4504.7 1232.17  4577.1 1230.99
  4746.5 1230.19  4791.1 1230.77  4931.0 1228.22  4962.8 1225.54  4977.9 1225.32
  4983.9 1222.70  5000.0 1219.76  5000.5 1216.76  5006.9 1216.76  5007.4 1219.76
  5034.8 1227.21  5087.5 1231.74  5128.1 1235.58  5206.3 1246.79  5221.4 1247.71
  5247.2 1252.21  5252.5 1252.05  5269.8 1255.64  5278.3 1255.96  5283.6 1257.57
  5291.0 1257.12  5309.4 1258.94  5345.8 1263.93  5354.5 1262.89  5402.8 1264.75
#Mann=6,-1,0
  4302.6    0.05       0  4577.1    0.12       0  4746.5    0.05       0
  5000.0    0.05       0  5007.4    0.05       0  5087.5    0.12       0
Bank Sta=5000,5007.4
Exp/Cntr=0.3,0.1

Type RM Length L Ch R = 1,3345,536,536,536
BEGIN DESCRIPTION:
SANDY 10 6.0
END DESCRIPTION:
XS GIS Cut Line= 3
      2795310.25     10158014.08      2795525.11     10158708.78
      2795716.06     10158933.15
#Sta/Elev= 30
  4408.9 1246.27  4554.4 1236.52  4574.9 1235.98  4596.3 1234.03  4732.4 1227.75
  4851.6 1227.04  4899.9 1224.41  4973.1 1225.24  4987.3 1222.64  4990.4 1219.07
  4990.9 1216.07  4997.3 1216.07  4997.8 1219.07  5014.7 1219.30  5025.5 1221.75
  5070.5 1225.00  5117.8 1231.58  5168.0 1235.40  5238.7 1237.91  5246.5 1237.11
  5253.0 1238.65  5267.3 1237.64  5288.2 1238.68  5310.2 1238.64  5373.8 1242.75
  5402.4 1243.14  5409.0 1244.72  5416.7 1244.67  5423.2 1245.98  5430.7 1246.19
#Mann=4,-1,0
  4408.9    0.05       0  4990.4    0.05       0  4997.8    0.05       0
  5070.5    0.12       0
Bank Sta=4990.4,4997.8
Exp/Cntr=0.3,0.1

Type RM Length L Ch R = 1,2809,342,342,342
BEGIN DESCRIPTION:
Mapping XS 5b57a0d6
END DESCRIPTION:
XS GIS Cut Line= 3
      2794835.20     10158393.66      2795193.29     10158723.11
      2795697.00     10158949.90
#Sta/Elev= 30
  4817.8 1234.61  4824.8 1233.34  4832.0 1233.75  4966.6 1225.61  4980.8 1221.29
  4987.6 1214.48  4995.0 1215.66  4998.1 1214.45  4998.6 1211.45  5005.0 1211.45
  5005.5 1214.45  5036.9 1219.72  5051.1 1220.57  5107.8 1220.97  5164.5 1223.93
  5235.4 1224.81  5263.8 1223.68  5320.0 1223.62  5366.3 1224.49  5383.8 1225.35
  5389.5 1226.76  5412.6 1229.28  5449.6 1231.44  5493.4 1232.42  5585.6 1229.91
  5649.2 1231.70  5706.8 1233.30  5758.6 1237.11  5781.7 1237.90  5856.8 1244.47
#Mann=4,-1,0
  4817.8    0.05       0  4998.1    0.05       0  5005.5    0.05       0
  5649.2    0.12       0
Bank Sta=4998.1,5005.5
Exp/Cntr=0.3,0.1

Type RM Length L Ch R = 1,2467,418,418,418
BEGIN DESCRIPTION:
SANDY 10 5.0
END DESCRIPTION:
XS GIS Cut Line= 3
      2794625.10     10158890.21      2795069.18     10158807.82
      2795634.96     10158959.45
#Sta/Elev= 30
  4653.8 1230.85  4837.5 1226.37  4868.0 1223.41  4923.6 1220.83  4969.7 1217.14
  4994.7 1212.58  4996.4 1211.09  4996.9 1208.09  5003.4 1208.09  5003.9 1211.09
  5010.4 1211.42  5021.6 1213.87  5047.5 1218.21  5091.7 1221.97  5226.9 1220.90
  5267.5 1221.79  5296.5 1223.33  5301.7 1222.78  5336.6 1229.00  5341.7 1228.27
  5371.0 1229.99  5422.8 1227.48  5496.4 1228.20  5526.3 1229.58  5536.7 1229.14
  5547.0 1230.59  5578.1 1230.72  5646.4 1236.25  5686.4 1237.55  5691.2 1238.72
#Mann=6,-1,0
  4653.8    0.05       0  4923.6    0.12       0  4996.4    0.07       0
  5003.9    0.12       0  5021.6    0.05       0  5496.4    0.12       0
Bank Sta=4996.4,5003.9
Exp/Cntr=0.3,0.1

Type RM Length L Ch R = 1,2049,434,434,434
BEGIN DESCRIPTION:
SANDY 10 4.0
END DESCRIPTION:
XS GIS Cut Line= 3
      2794906.84     10159446.40      2795195.40     10159109.34
      2795778.11     10159088.34
#Sta/Elev= 30
  4681.5 1244.84  4734.5 1244.11  4775.5 1241.27  4839.2 1229.77  4853.5 1228.22
  4867.7 1227.40  4874.3 1229.22  4882.0 1228.08  4902.9 1228.31  4928.7 1225.77
  4945.7 1224.65  4959.9 1221.75  4988.5 1207.05  4998.0 1206.47  4998.5 1203.47
  5005.0 1203.47  5005.5 1206.47  5030.2 1212.95  5054.3 1215.98  5080.7 1217.54
  5154.9 1216.50  5255.6 1217.32  5385.7 1220.86  5485.7 1227.69  5545.8 1235.61
  5574.7 1237.61  5605.8 1241.21  5645.8 1249.79  5675.9 1254.00  5708.3 1256.49
#Mann=7,-1,0
  4681.5    0.12       0  4734.5    0.05       0  4928.7    0.12       0
  4998.0    0.07       0  5005.5    0.12       0  5054.3    0.05       0
  5574.7    0.12       0
Bank Sta=4998,5005.5
Exp/Cntr=0.3,0.1

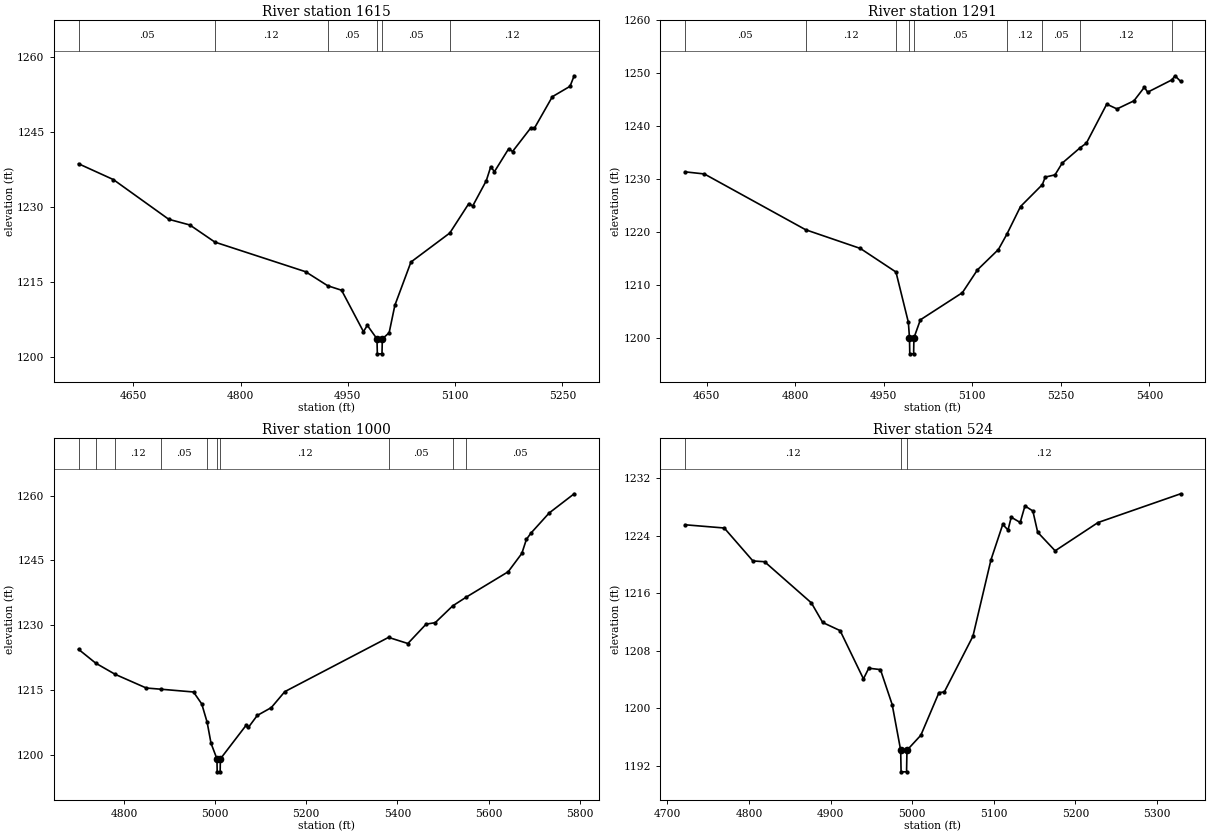
Type RM Length L Ch R = 1,1615,324,324,324
BEGIN DESCRIPTION:
SANDY 10 3.0
END DESCRIPTION:
XS GIS Cut Line= 3
      2795073.92     10159565.78      2795331.75     10159460.74
      2795721.10     10159318.29
#Sta/Elev= 30
  4573.5 1238.62  4622.2 1235.45  4699.7 1227.49  4729.2 1226.35  4764.2 1222.92
  4891.0 1216.99  4921.9 1214.18  4941.3 1213.28  4971.9 1204.98  4977.3 1206.25
  4990.8 1203.54  4991.3 1200.54  4997.8 1200.54  4998.3 1203.54  5007.8 1204.76
  5015.8 1210.26  5038.3 1218.93  5092.6 1224.74  5119.2 1230.64  5124.6 1230.15
  5143.6 1235.21  5149.8 1237.98  5155.1 1237.05  5175.0 1241.64  5180.3 1241.06
  5205.5 1245.74  5210.8 1245.71  5236.0 1252.05  5260.7 1254.13  5266.5 1256.24
#Mann=6,-1,0
  4573.5    0.05       0  4764.2    0.12       0  4921.9    0.05       0
  4990.8    0.05       0  4998.3    0.05       0  5092.6    0.12       0
Bank Sta=4990.8,4998.3
Exp/Cntr=0.3,0.1

Type RM Length L Ch R = 1,1291,291,291,291
BEGIN DESCRIPTION:
Mapping XS 8467121a
END DESCRIPTION:
XS GIS Cut Line= 3
      2795083.45     10159797.33      2795644.46     10159694.68
      2795754.27     10159448.81
#Sta/Elev= 30
  4613.4 1231.42  4646.2 1231.02  4817.9 1220.48  4910.5 1216.95  4970.8 1212.50
  4991.8 1203.01  4993.7 1200.05  4994.2 1197.05  5000.7 1197.05  5001.2 1200.05
  5012.1 1203.47  5083.3 1208.60  5108.9 1212.92  5144.3 1216.75  5158.5 1219.61
  5181.8 1224.87  5218.8 1229.01  5223.6 1230.43  5240.2 1230.85  5252.3 1233.05
  5283.1 1236.00  5293.3 1236.83  5327.8 1244.20  5345.2 1243.30  5373.9 1244.83
  5391.6 1247.40  5397.1 1246.46  5438.1 1248.78  5443.5 1249.56  5453.0 1248.50
#Mann=9,-1,0
  4613.4    0.05       0  4817.9    0.12       0  4970.8    0.05       0
  4993.7    0.05       0  5001.2    0.05       0  5158.5    0.12       0
  5218.8    0.05       0  5283.1    0.12       0  5438.1    0.05       0
Bank Sta=4993.7,5001.2
Exp/Cntr=0.3,0.1

Type RM Length L Ch R = 1,1000,476,476,476
BEGIN DESCRIPTION:
SANDY 10 2.0
END DESCRIPTION:
XS GIS Cut Line= 3
      2795229.09     10160059.91      2795641.53     10159989.77
      2796310.46     10159985.91
#Sta/Elev= 30
  4700.3 1224.41  4738.1 1221.19  4780.8 1218.60  4849.0 1215.43  4881.7 1215.15
  4952.6 1214.51  4970.7 1211.73  4982.5 1207.48  4991.0 1202.62  5004.0 1199.00
  5004.5 1196.00  5011.0 1196.00  5011.5 1199.00  5068.0 1206.80  5073.1 1206.32
  5092.4 1209.07  5123.2 1210.89  5152.8 1214.59  5380.4 1227.17  5422.8 1225.75
  5462.8 1230.24  5482.8 1230.58  5521.1 1234.47  5551.0 1236.51  5642.8 1242.38
  5672.8 1246.63  5682.8 1249.89  5692.8 1251.34  5732.8 1256.01  5787.6 1260.46
#Mann=10,-1,0
  4700.3    0.12       0  4738.1    0.05       0  4780.8    0.12       0
  4881.7    0.05       0  4982.5    0.12       0  5004.0    0.07       0
  5011.5    0.12       0  5380.4    0.05       0  5521.1    0.12       0
  5551.0    0.05       0
Bank Sta=5004,5011.5
Exp/Cntr=0.3,0.1

Type RM Length L Ch R = 1,524,0,0,0
BEGIN DESCRIPTION:
SANDY 10 1.0
END DESCRIPTION:
XS GIS Cut Line= 3
      2795198.05     10160143.44      2795455.68     10160453.11
      2795631.01     10160557.92
#Sta/Elev= 30
  4721.7 1225.51  4769.8 1225.06  4804.9 1220.48  4819.2 1220.37  4876.5 1214.65
  4890.4 1211.92  4911.7 1210.79  4940.3 1204.08  4946.8 1205.56  4961.1 1205.37
  4975.5 1200.50  4985.9 1194.15  4986.4 1191.15  4993.1 1191.15  4993.6 1194.15
  5010.6 1196.24  5032.8 1202.17  5039.3 1202.25  5074.4 1210.01  5096.5 1220.64
  5110.9 1225.55  5117.4 1224.79  5121.3 1226.56  5132.3 1225.83  5138.1 1228.13
  5147.8 1227.43  5153.7 1224.47  5175.1 1221.89  5227.6 1225.82  5328.8 1229.82
#Mann=3,-1,0
  4721.7    0.12       0  4985.9    0.07       0  4993.6    0.12       0
Bank Sta=4985.9,4993.6
Exp/Cntr=0.3,0.1

Chan Stop Cuts=-1