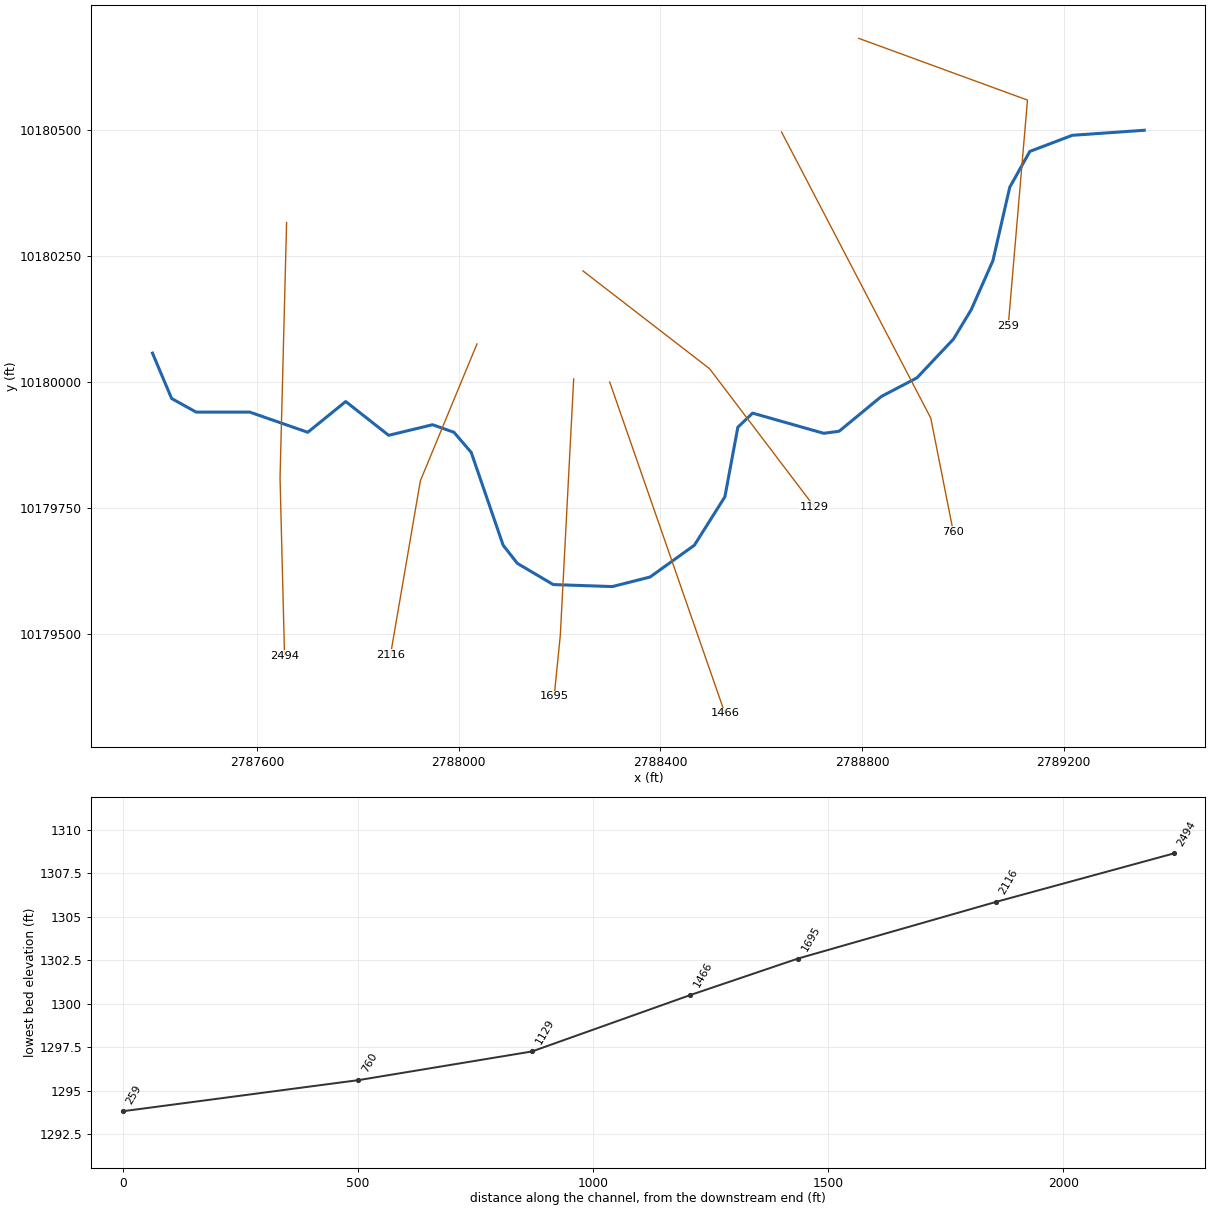
--- SANDY 15.prj (project) ---

Proj Title=SANDY 15 Base Level Engineering
Current Plan=p01
Default Exp/Contr=0.3,0.1
English Units
Geom File=g01
Flow File=f01
Plan File=p01
BEGIN DESCRIPTION:
SANDY 15
END DESCRIPTION:

--- SANDY 15.p01 (plan) ---

Plan Title=Multiple Run
Short Identifier=Multiple
Geom File=g01
Flow File=f01
Subcritical Flow
K Sum by GR= 0
Std Step Tol= 0.01
Critical Tol= 0.01
Num of Std Step Trials= 20
Max Error Tol= 0.3
Flow Tol Ratio= 0.001
Split Flow NTrial= 30
Split Flow Tol= 0.02
Split Flow Ratio= 0.02
Log Output Level= 0
Friction Slope Method= 1
Unsteady Friction Slope Method= 2
Unsteady Bridges Friction Slope Method= 1
Parabolic Critical Depth
Global Vel Dist=  1 , 1 , 1
Global Log Level= 0
CheckData=True
Encroach Param= -1, 0, 0, 0
BEGIN DESCRIPTION:
Multiple Run
END DESCRIPTION:

--- SANDY 15.f01 (steady flow) ---

Flow Title=Multiple
Number of Profiles=7
Profile Names=10-year,25-year,50-year,1pct_min,100-year,1pct_plu,500-year
River Rch & RM= SANDY 15,Reach-1,2494
      64     121     189      98     294     889     772
Boundary for River Rch & Prof#=SANDY 15,Reach-1,1
Up Type=0
Dn Type=3
Dn Slope=0.005
Boundary for River Rch & Prof#=SANDY 15,Reach-1,2
Up Type=0
Dn Type=3
Dn Slope=0.005
Boundary for River Rch & Prof#=SANDY 15,Reach-1,3
Up Type=0
Dn Type=3
Dn Slope=0.005
Boundary for River Rch & Prof#=SANDY 15,Reach-1,4
Up Type=0
Dn Type=3
Dn Slope=0.005
Boundary for River Rch & Prof#=SANDY 15,Reach-1,5
Up Type=0
Dn Type=3
Dn Slope=0.005
Boundary for River Rch & Prof#=SANDY 15,Reach-1,6
Up Type=0
Dn Type=3
Dn Slope=0.005
Boundary for River Rch & Prof#=SANDY 15,Reach-1,7
Up Type=0
Dn Type=3
Dn Slope=0.005

--- SANDY 15.g01 (geometry) ---

Geom Title=Existing Conditions

River Reach=SANDY 15,Reach-1
Reach XY= 30
      2787392.75     10180058.00      2787430.75     10179968.00
      2787479.50     10179941.00      2787585.75     10179941.00
      2787700.75     10179901.00      2787776.00     10179962.00
      2787861.25     10179895.00      2787948.25     10179916.00
      2787990.75     10179901.00      2788025.00     10179861.00
      2788088.25     10179677.00      2788116.50     10179641.00
      2788187.50     10179599.00      2788304.75     10179595.00
      2788379.75     10179614.00      2788467.50     10179677.00
      2788528.00     10179773.00      2788553.75     10179911.00
      2788583.00     10179939.00      2788724.00     10179899.00
      2788754.50     10179903.00      2788838.25     10179972.00
      2788909.00     10180009.00      2788981.50     10180086.00
      2789016.50     10180144.00      2789059.50     10180241.00
      2789093.00     10180387.00      2789132.75     10180458.00
      2789217.00     10180490.00      2789359.75     10180500.00

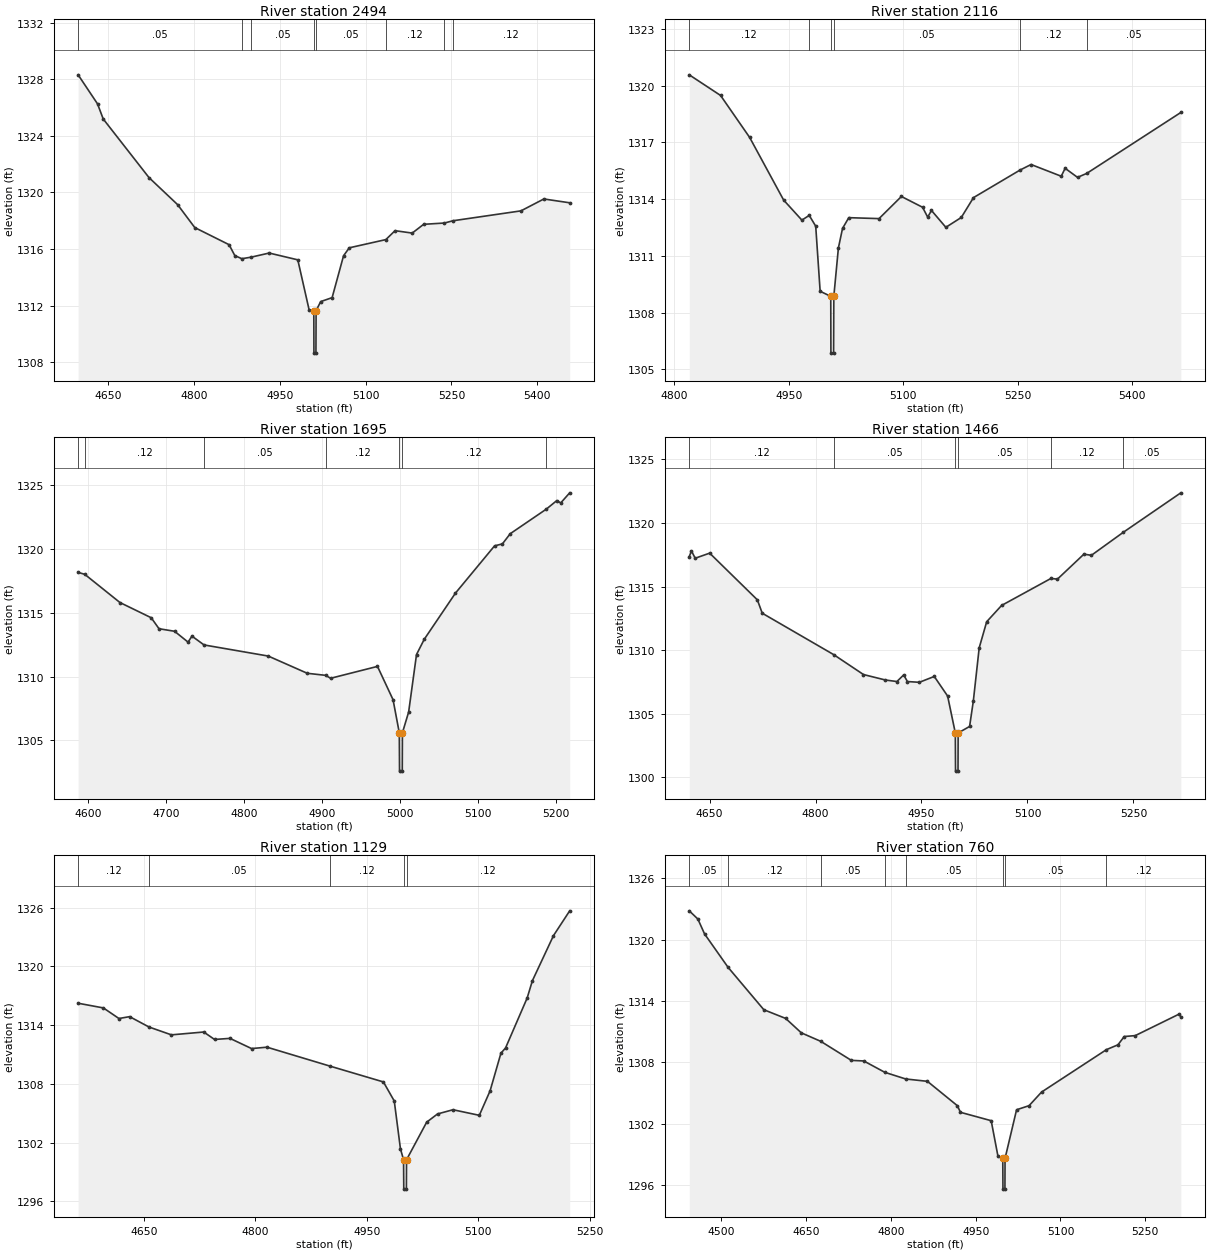
Type RM Length L Ch R = 1,2494,378,378,378
BEGIN DESCRIPTION:
SANDY 15 5.0
END DESCRIPTION:
XS GIS Cut Line= 3
      2787658.76     10180316.96      2787645.78     10179810.95
      2787654.68     10179457.93
#Sta/Elev= 30
  4597.5 1328.31  4631.4 1326.26  4641.4 1325.19  4721.4 1321.05  4771.4 1319.14
  4801.4 1317.52  4861.4 1316.31  4871.4 1315.54  4883.7 1315.32  4900.0 1315.43
  4931.5 1315.72  4981.5 1315.24  5001.5 1311.67  5009.5 1311.65  5009.7 1308.65
  5013.2 1308.65  5013.5 1311.65  5021.5 1312.29  5041.5 1312.57  5061.5 1315.53
  5071.5 1316.09  5135.4 1316.67  5151.5 1317.30  5181.5 1317.13  5201.5 1317.75
  5237.8 1317.84  5252.6 1318.00  5371.6 1318.70  5411.6 1319.54  5456.8 1319.27
#Mann=8,-1,0
  4597.5    0.05       0  4883.7    0.12       0  4900.0    0.05       0
  5009.5    0.05       0  5013.5    0.05       0  5135.4    0.12       0
  5237.8    0.05       0  5252.6    0.12       0
Bank Sta=5009.5,5013.5
Exp/Cntr=0.3,0.1

Type RM Length L Ch R = 1,2116,421,421,421
BEGIN DESCRIPTION:
SANDY 15 4.0
END DESCRIPTION:
XS GIS Cut Line= 3
      2788036.31     10180076.17      2787924.07     10179804.74
      2787864.88     10179459.80
#Sta/Elev= 30
  4819.7 1320.57  4860.7 1319.48  4898.8 1317.26  4943.3 1313.95  4967.2 1312.89
  4976.8 1313.14  4985.3 1312.57  4991.1 1309.13  5005.0 1308.86  5005.2 1305.86
  5008.7 1305.86  5009.0 1308.86  5015.0 1311.42  5020.4 1312.45  5028.6 1313.02
  5068.2 1312.97  5097.5 1314.14  5125.2 1313.57  5131.9 1313.05  5136.9 1313.40
  5155.7 1312.51  5175.9 1313.03  5191.9 1314.08  5253.0 1315.54  5267.3 1315.83
  5306.8 1315.21  5311.9 1315.63  5328.1 1315.15  5340.2 1315.36  5463.4 1318.58
#Mann=6,-1,0
  4819.7    0.12       0  4976.8    0.05       0  5005.0    0.05       0
  5009.0    0.05       0  5253.0    0.12       0  5340.2    0.05       0
Bank Sta=5005,5009
Exp/Cntr=0.3,0.1

Type RM Length L Ch R = 1,1695,229,229,229
BEGIN DESCRIPTION:
SANDY 15 3.0
END DESCRIPTION:
XS GIS Cut Line= 3
      2788228.16     10180006.77      2788201.63     10179498.62
      2788189.48     10179377.17
#Sta/Elev= 30
  4587.0 1318.16  4595.5 1318.01  4640.7 1315.80  4680.8 1314.61  4690.8 1313.75
  4710.8 1313.55  4728.1 1312.70  4733.1 1313.17  4748.6 1312.48  4831.0 1311.61
  4881.1 1310.26  4904.6 1310.10  4911.1 1309.87  4971.2 1310.80  4991.2 1308.19
  4999.2 1305.60  4999.5 1302.60  5003.0 1302.60  5003.2 1305.60  5011.2 1307.23
  5021.3 1311.73  5031.3 1312.93  5071.3 1316.54  5121.5 1320.24  5131.5 1320.39
  5141.6 1321.19  5187.8 1323.11  5201.3 1323.78  5206.4 1323.60  5217.9 1324.39
#Mann=7,-1,0
  4587.0    0.05       0  4595.5    0.12       0  4748.6    0.05       0
  4904.6    0.12       0  4999.2    0.07       0  5003.2    0.12       0
  5187.8    0.05       0
Bank Sta=4999.2,5003.2
Exp/Cntr=0.3,0.1

Type RM Length L Ch R = 1,1466,337,337,337
BEGIN DESCRIPTION:
Mapping XS 2aae7e9d
END DESCRIPTION:
XS GIS Cut Line= 2
      2788299.58     10180000.70      2788528.16     10179343.52
#Sta/Elev= 30
  4621.3 1317.35  4624.4 1317.81  4629.7 1317.23  4650.2 1317.63  4717.7 1313.96
  4724.6 1312.91  4825.6 1309.66  4867.9 1308.09  4899.0 1307.66  4915.2 1307.54
  4924.8 1308.06  4930.1 1307.54  4947.0 1307.48  4968.1 1307.94  4987.0 1306.40
  4997.9 1303.50  4998.2 1300.50  5001.7 1300.50  5001.9 1303.50  5018.1 1304.01
  5023.4 1306.01  5031.7 1310.19  5042.3 1312.24  5063.4 1313.52  5133.2 1315.64
  5142.5 1315.59  5179.9 1317.55  5190.5 1317.46  5235.7 1319.27  5317.1 1322.37
#Mann=6,-1,0
  4621.3    0.12       0  4825.6    0.05       0  4997.9    0.05       0
  5001.9    0.05       0  5133.2    0.12       0  5235.7    0.05       0
Bank Sta=4997.9,5001.9
Exp/Cntr=0.3,0.1

Type RM Length L Ch R = 1,1129,369,369,369
BEGIN DESCRIPTION:
SANDY 15 2.0
END DESCRIPTION:
XS GIS Cut Line= 3
      2788246.54     10180221.07      2788497.55     10180027.20
      2788705.67     10179753.13
#Sta/Elev= 30
  4561.5 1316.24  4595.5 1315.76  4616.4 1314.68  4630.8 1314.87  4656.9 1313.81
  4687.0 1313.01  4730.5 1313.30  4745.0 1312.54  4765.8 1312.65  4794.8 1311.61
  4815.6 1311.75  4899.7 1309.83  4972.2 1308.20  4986.8 1306.25  4995.1 1301.37
  4999.3 1300.25  4999.6 1297.25  5003.1 1297.25  5003.3 1300.25  5030.4 1304.09
  5045.0 1304.93  5065.8 1305.36  5101.2 1304.79  5115.7 1307.29  5130.3 1311.14
  5136.5 1311.67  5165.6 1316.78  5172.6 1318.54  5201.0 1323.15  5222.8 1325.68
#Mann=5,-1,0
  4561.5    0.12       0  4656.9    0.05       0  4899.7    0.12       0
  4999.3    0.07       0  5003.3    0.12       0
Bank Sta=4999.3,5003.3
Exp/Cntr=0.3,0.1

Type RM Length L Ch R = 1,760,501,501,501
BEGIN DESCRIPTION:
Mapping XS 71e06fa0
END DESCRIPTION:
XS GIS Cut Line= 3
      2788640.43     10180496.55      2788936.34     10179929.24
      2788980.96     10179704.07
#Sta/Elev= 30
  4443.5 1322.81  4458.7 1322.01  4470.6 1320.55  4512.1 1317.29  4575.4 1313.14
  4614.0 1312.29  4641.7 1310.88  4676.1 1310.05  4730.1 1308.19  4752.2 1308.13
  4789.4 1307.02  4826.3 1306.37  4864.7 1306.14  4917.6 1303.76  4923.2 1303.11
  4977.5 1302.29  4989.5 1298.81  4998.0 1298.60  4998.3 1295.60  5001.8 1295.60
  5002.0 1298.60  5022.4 1303.36  5044.5 1303.76  5066.6 1305.09  5181.4 1309.24
  5201.7 1309.71  5212.8 1310.52  5232.3 1310.61  5310.1 1312.72  5312.9 1312.43
#Mann=8,-1,0
  4443.5    0.05       0  4512.1    0.12       0  4676.1    0.05       0
  4789.4    0.12       0  4826.3    0.05       0  4998.0    0.05       0
  5002.0    0.05       0  5181.4    0.12       0
Bank Sta=4998,5002
Exp/Cntr=0.3,0.1

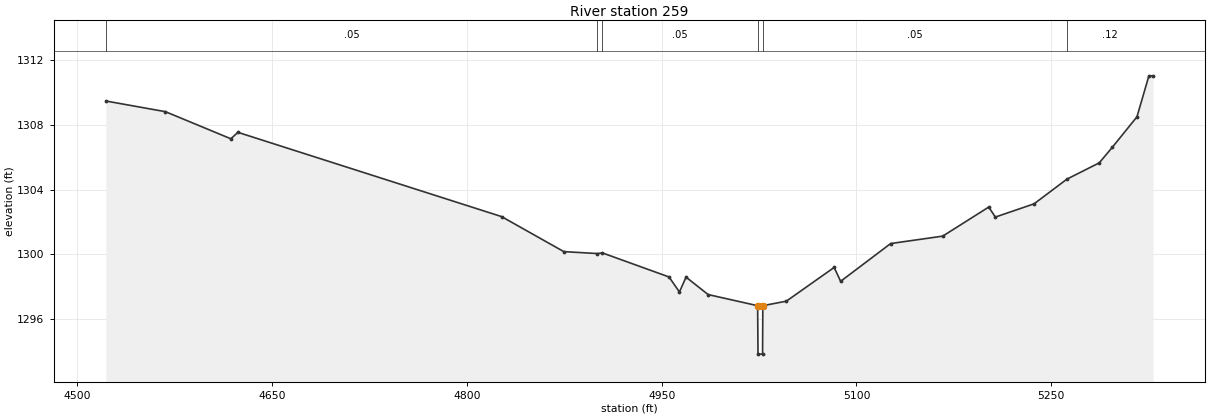
Type RM Length L Ch R = 1,259,0,0,0
BEGIN DESCRIPTION:
SANDY 15 1.0
END DESCRIPTION:
XS GIS Cut Line= 3
      2788793.43     10180682.33      2789128.18     10180559.86
      2789089.96     10180111.83
#Sta/Elev= 30
  4522.2 1309.49  4568.0 1308.83  4618.4 1307.15  4623.8 1307.55  4826.8 1302.33
  4874.7 1300.16  4900.5 1300.04  4904.4 1300.08  4955.7 1298.59  4963.7 1297.66
  4968.8 1298.58  4985.8 1297.50  5023.9 1296.81  5024.2 1293.81  5027.7 1293.81
  5027.9 1296.81  5046.0 1297.09  5082.8 1299.18  5087.8 1298.32  5126.3 1300.66
  5166.4 1301.12  5201.8 1302.92  5206.9 1302.30  5236.7 1303.12  5262.0 1304.65
  5286.9 1305.66  5296.9 1306.62  5315.9 1308.51  5325.1 1311.05  5328.3 1311.05
#Mann=6,-1,0
  4522.2    0.05       0  4900.5    0.12       0  4904.4    0.05       0
  5023.9    0.05       0  5027.9    0.05       0  5262.0    0.12       0
Bank Sta=5023.9,5027.9
Exp/Cntr=0.3,0.1

Chan Stop Cuts=-1