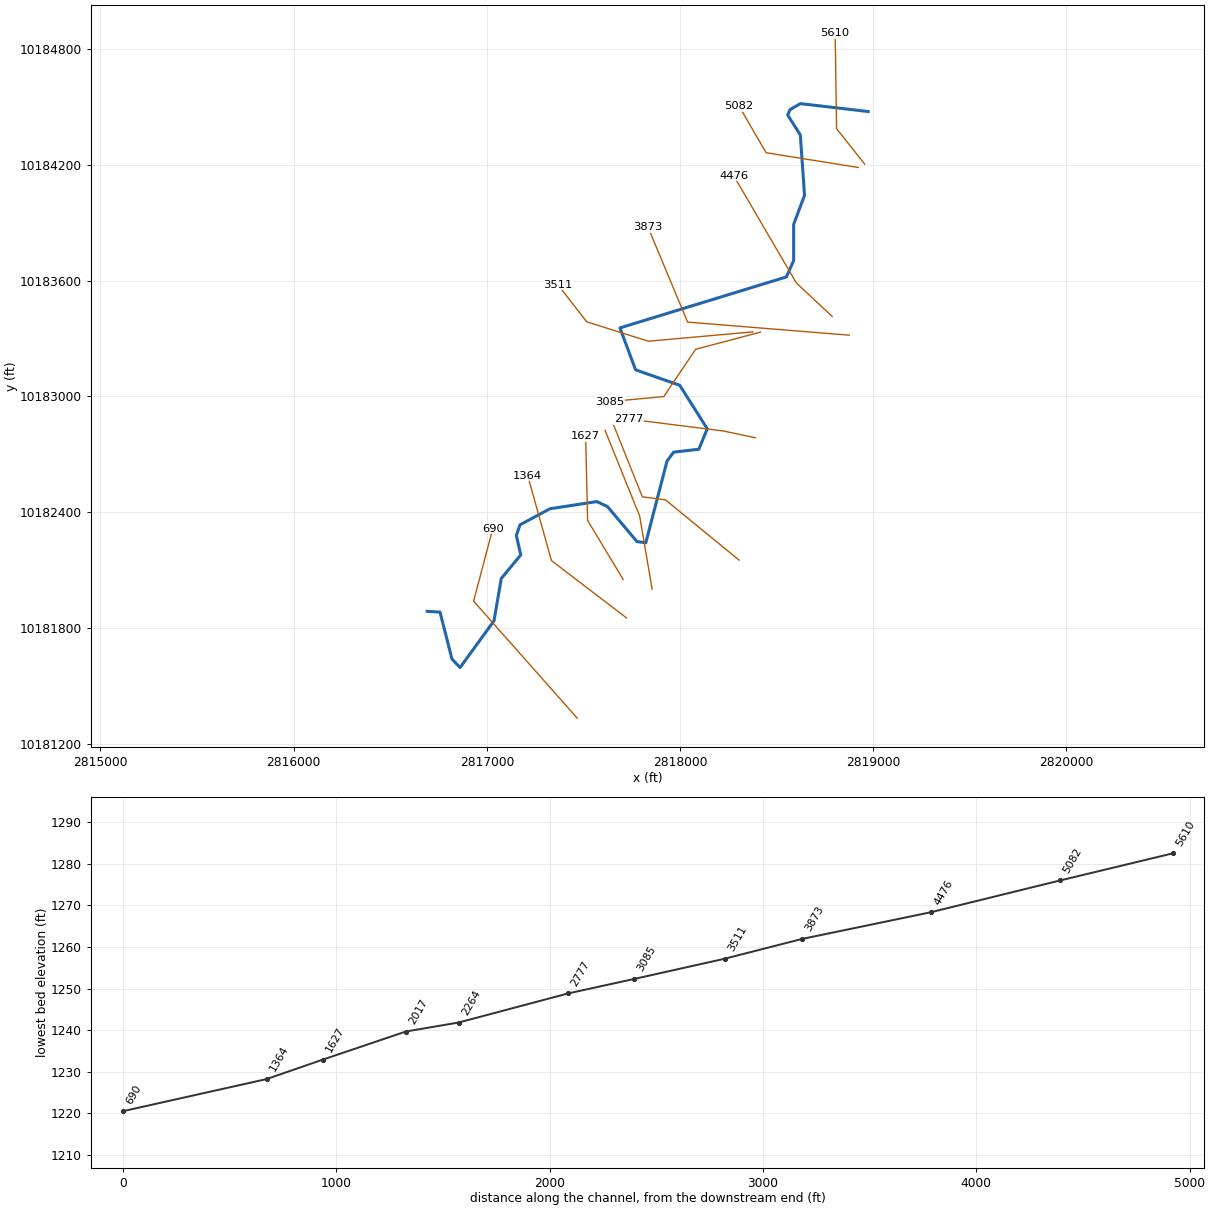
--- SANDY 24.prj (project) ---

Proj Title=SANDY 24 Base Level Engineering
Current Plan=p01
Default Exp/Contr=0.3,0.1
English Units
Geom File=g01
Flow File=f01
Plan File=p01
BEGIN DESCRIPTION:
SANDY 24
END DESCRIPTION:

--- SANDY 24.p01 (plan) ---

Plan Title=Multiple Run
Short Identifier=Multiple
Geom File=g01
Flow File=f01
Subcritical Flow
K Sum by GR= 0
Std Step Tol= 0.01
Critical Tol= 0.01
Num of Std Step Trials= 20
Max Error Tol= 0.3
Flow Tol Ratio= 0.001
Split Flow NTrial= 30
Split Flow Tol= 0.02
Split Flow Ratio= 0.02
Log Output Level= 0
Friction Slope Method= 1
Unsteady Friction Slope Method= 2
Unsteady Bridges Friction Slope Method= 1
Parabolic Critical Depth
Global Vel Dist=  1 , 1 , 1
Global Log Level= 0
CheckData=True
Encroach Param= -1, 0, 0, 0
BEGIN DESCRIPTION:
Multiple Run
END DESCRIPTION:

--- SANDY 24.f01 (steady flow) ---

Flow Title=Multiple
Number of Profiles=7
Profile Names=10-year,25-year,50-year,1pct_min,100-year,1pct_plu,500-year
River Rch & RM= SANDY 24,Reach-1,5610
      70     130     201     104     313     946     821
River Rch & RM= SANDY 24,Reach-1,4476
     303     682    1151     635    1918    5794    5660
Boundary for River Rch & Prof#=SANDY 24,Reach-1,1
Up Type=0
Dn Type=3
Dn Slope=0.005
Boundary for River Rch & Prof#=SANDY 24,Reach-1,2
Up Type=0
Dn Type=3
Dn Slope=0.005
Boundary for River Rch & Prof#=SANDY 24,Reach-1,3
Up Type=0
Dn Type=3
Dn Slope=0.005
Boundary for River Rch & Prof#=SANDY 24,Reach-1,4
Up Type=0
Dn Type=3
Dn Slope=0.005
Boundary for River Rch & Prof#=SANDY 24,Reach-1,5
Up Type=0
Dn Type=3
Dn Slope=0.005
Boundary for River Rch & Prof#=SANDY 24,Reach-1,6
Up Type=0
Dn Type=3
Dn Slope=0.005
Boundary for River Rch & Prof#=SANDY 24,Reach-1,7
Up Type=0
Dn Type=3
Dn Slope=0.005

--- SANDY 24.g01 (geometry) ---

Geom Title=Existing Conditions

River Reach=SANDY 24,Reach-1
Reach XY= 30
      2818974.00     10184475.00      2818622.75     10184516.00
      2818569.75     10184485.00      2818557.25     10184457.00
      2818622.75     10184354.00      2818644.50     10184041.00
      2818588.25     10183891.00      2818588.25     10183704.00
      2818550.75     10183619.00      2817689.00     10183355.00
      2817770.00     10183138.00      2817998.50     10183058.00
      2818141.00     10182833.00      2818097.50     10182727.00
      2817967.00     10182712.00      2817932.75     10182666.00
      2817823.00     10182243.00      2817777.00     10182249.00
      2817624.75     10182430.00      2817569.75     10182456.00
      2817327.00     10182419.00      2817172.00     10182336.00
      2817152.75     10182281.00      2817175.50     10182180.00
      2817074.75     10182058.00      2817037.25     10181839.00
      2816861.50     10181597.00      2816819.50     10181641.00
      2816757.75     10181884.00      2816691.25     10181888.00

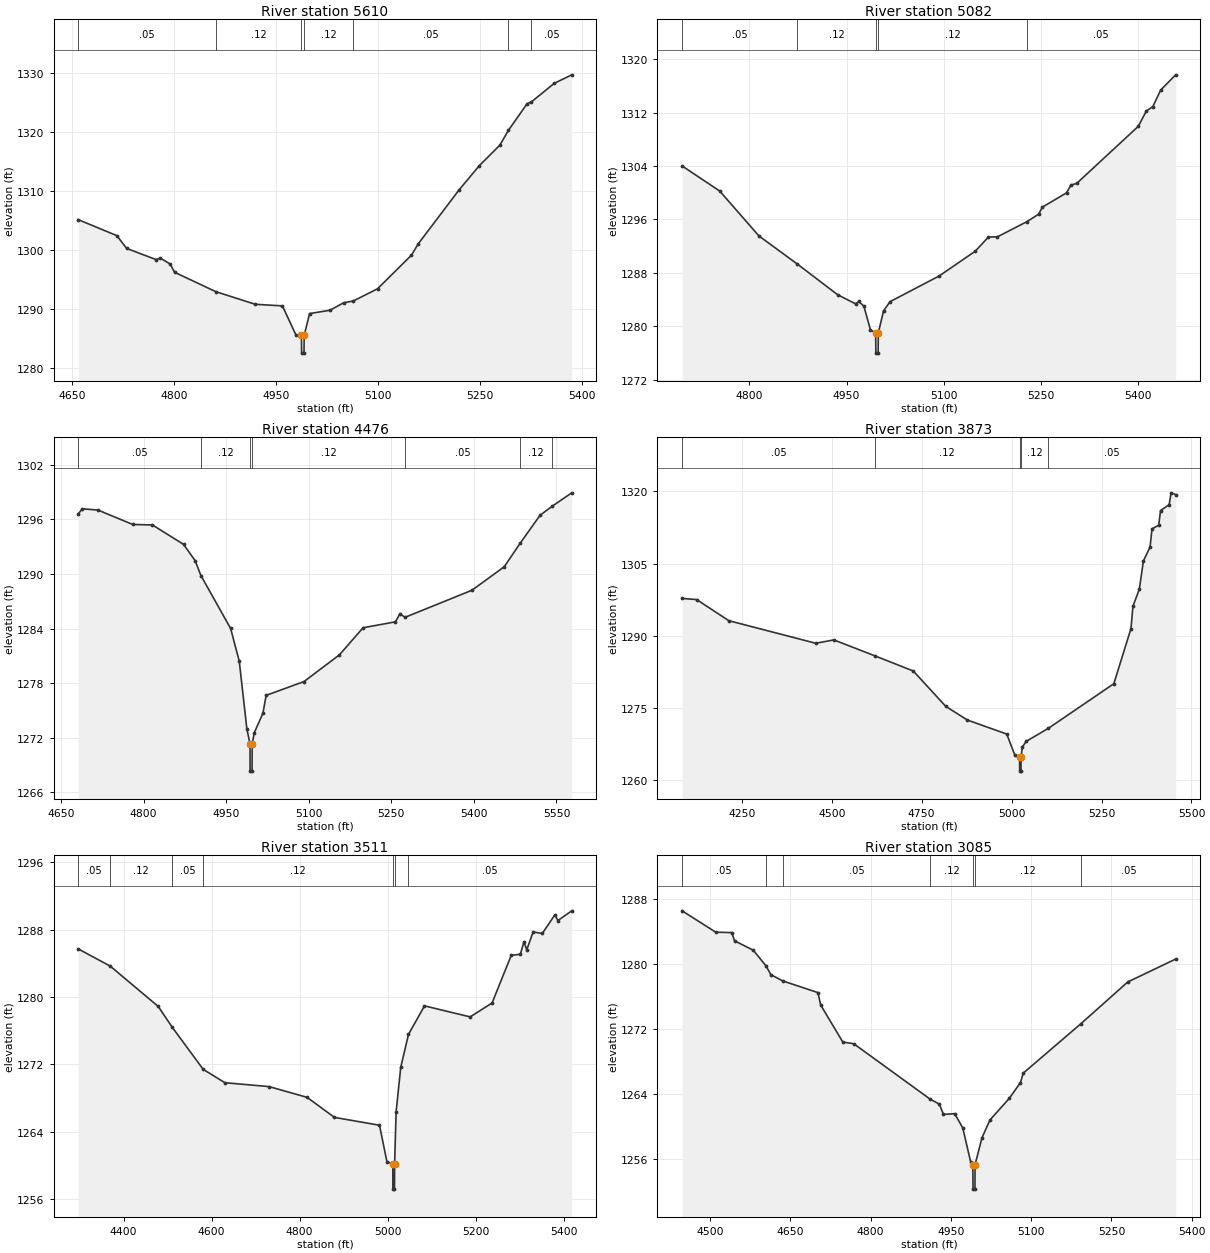
Type RM Length L Ch R = 1,5610,528,528,528
BEGIN DESCRIPTION:
SANDY 24 11.0
END DESCRIPTION:
XS GIS Cut Line= 3
      2818955.70     10184203.09      2818810.37     10184386.58
      2818803.17     10184878.96
#Sta/Elev= 30
  4658.5 1305.15  4715.4 1302.43  4729.8 1300.26  4773.1 1298.37  4779.5 1298.62
  4793.9 1297.61  4800.3 1296.22  4860.9 1292.93  4919.1 1290.78  4959.1 1290.51
  4979.1 1285.54  4987.1 1285.49  4987.4 1282.49  4990.9 1282.49  4991.1 1285.49
  4999.1 1289.20  5029.1 1289.77  5049.1 1291.03  5063.4 1291.34  5099.1 1293.41
  5149.1 1299.12  5159.1 1301.05  5219.1 1310.19  5249.1 1314.33  5279.1 1317.78
  5291.8 1320.30  5319.1 1324.80  5325.7 1325.14  5359.2 1328.28  5385.0 1329.73
#Mann=7,-1,0
  4658.5    0.05       0  4860.9    0.12       0  4987.1    0.07       0
  4991.1    0.12       0  5063.4    0.05       0  5291.8    0.12       0
  5325.7    0.05       0
Bank Sta=4987.1,4991.1
Exp/Cntr=0.3,0.1

Type RM Length L Ch R = 1,5082,606,606,606
BEGIN DESCRIPTION:
SANDY 24 10.0
END DESCRIPTION:
XS GIS Cut Line= 3
      2818922.93     10184185.41      2818445.52     10184261.80
      2818305.68     10184503.12
#Sta/Elev= 30
  4696.0 1304.00  4754.0 1300.25  4814.7 1293.52  4874.2 1289.30  4936.3 1284.72
  4963.9 1283.36  4969.0 1283.71  4976.8 1283.00  4986.9 1279.48  4995.0 1278.98
  4995.3 1275.98  4998.8 1275.98  4999.0 1278.98  5007.2 1282.32  5017.3 1283.69
  5093.1 1287.53  5148.9 1291.24  5169.2 1293.36  5183.1 1293.39  5228.4 1295.65
  5246.8 1296.78  5252.5 1297.83  5289.8 1299.97  5296.6 1301.13  5305.6 1301.39
  5400.6 1309.92  5413.2 1312.23  5423.2 1312.89  5435.3 1315.36  5458.4 1317.64
#Mann=5,-1,0
  4696.0    0.05       0  4874.2    0.12       0  4995.0    0.07       0
  4999.0    0.12       0  5228.4    0.05       0
Bank Sta=4995,4999
Exp/Cntr=0.3,0.1

Type RM Length L Ch R = 1,4476,603,603,603
BEGIN DESCRIPTION:
SANDY 24 9.0
END DESCRIPTION:
XS GIS Cut Line= 3
      2818787.52     10183414.59      2818601.77     10183588.18
      2818278.08     10184142.68
#Sta/Elev= 30
  4681.4 1296.60  4688.7 1297.17  4717.0 1297.04  4780.5 1295.45  4816.2 1295.40
  4872.8 1293.26  4893.8 1291.47  4904.2 1289.84  4958.2 1284.02  4973.9 1280.42
  4987.7 1272.98  4993.4 1271.34  4993.6 1268.34  4997.1 1268.34  4997.4 1271.34
  5001.2 1272.56  5016.9 1274.71  5022.7 1276.67  5091.3 1278.18  5155.8 1281.12
  5198.8 1284.10  5257.5 1284.75  5265.6 1285.63  5275.1 1285.25  5396.4 1288.22
  5455.1 1290.80  5484.3 1293.41  5520.3 1296.47  5542.1 1297.45  5577.7 1298.93
#Mann=7,-1,0
  4681.4    0.05       0  4904.2    0.12       0  4993.4    0.07       0
  4997.4    0.12       0  5275.1    0.05       0  5484.3    0.12       0
  5542.1    0.05       0
Bank Sta=4993.4,4997.4
Exp/Cntr=0.3,0.1

Type RM Length L Ch R = 1,3873,362,362,362
BEGIN DESCRIPTION:
SANDY 24 8.0
END DESCRIPTION:
XS GIS Cut Line= 3
      2818876.06     10183317.35      2818039.27     10183385.06
      2817834.43     10183876.33
#Sta/Elev= 30
  4084.2 1297.76  4124.7 1297.53  4213.8 1293.15  4455.8 1288.46  4506.0 1289.16
  4619.4 1285.87  4726.7 1282.71  4817.0 1275.37  4877.2 1272.53  4986.6 1269.62
  5008.3 1265.38  5022.2 1264.93  5022.5 1261.93  5026.1 1261.93  5026.3 1264.93
  5030.0 1266.95  5040.8 1268.11  5102.6 1270.83  5284.2 1280.07  5331.9 1291.52
  5337.3 1296.13  5355.0 1299.66  5366.5 1305.56  5384.9 1308.43  5390.3 1312.21
  5408.8 1312.94  5414.2 1316.00  5438.0 1317.23  5443.4 1319.68  5456.0 1319.31
#Mann=5,-1,0
  4084.2    0.05       0  4619.4    0.12       0  5022.2    0.07       0
  5026.3    0.12       0  5102.6    0.05       0
Bank Sta=5022.2,5026.3
Exp/Cntr=0.3,0.1

Type RM Length L Ch R = 1,3511,426,426,426
BEGIN DESCRIPTION:
SANDY 24 7.0
END DESCRIPTION:
XS GIS Cut Line= 4
      2818377.77     10183334.71      2817836.14     10183286.10
      2817516.70     10183386.80      2817367.96     10183578.78
#Sta/Elev= 30
  4296.8 1285.72  4369.6 1283.67  4478.5 1278.89  4510.6 1276.40  4580.8 1271.41
  4630.2 1269.82  4730.6 1269.36  4817.0 1268.08  4879.2 1265.70  4981.5 1264.77
  4998.4 1260.46  5011.8 1260.18  5012.0 1257.18  5015.6 1257.18  5015.9 1260.18
  5019.3 1266.36  5029.8 1271.64  5047.3 1275.55  5083.8 1278.95  5187.6 1277.64
  5237.4 1279.29  5280.9 1284.95  5301.7 1285.08  5309.8 1286.57  5316.2 1285.61
  5330.7 1287.73  5351.5 1287.55  5380.5 1289.79  5386.8 1289.08  5418.4 1290.24
#Mann=7,-1,0
  4296.8    0.05       0  4369.6    0.12       0  4510.6    0.05       0
  4580.8    0.12       0  5011.8    0.07       0  5015.9    0.12       0
  5047.3    0.05       0
Bank Sta=5011.8,5015.9
Exp/Cntr=0.3,0.1

Type RM Length L Ch R = 1,3085,308,308,308
BEGIN DESCRIPTION:
Mapping XS da7e1b2c
END DESCRIPTION:
XS GIS Cut Line= 4
      2818415.98     10183332.97      2818080.94     10183244.43
      2817916.01     10182999.64      2817636.52     10182973.60
#Sta/Elev= 30
  4447.7 1286.57  4510.5 1283.94  4540.5 1283.89  4545.6 1282.88  4580.7 1281.72
  4604.6 1279.78  4613.5 1278.71  4635.7 1277.94  4701.5 1276.50  4706.7 1274.97
  4748.0 1270.41  4768.6 1270.20  4911.2 1263.38  4928.5 1262.77  4936.2 1261.50
  4957.2 1261.59  4972.2 1259.84  4987.1 1255.63  4991.1 1255.30  4991.4 1252.30
  4995.0 1252.30  4995.2 1255.30  5008.1 1258.62  5023.1 1260.82  5059.1 1263.47
  5080.1 1265.42  5085.2 1266.58  5193.4 1272.69  5280.6 1277.81  5370.1 1280.63
#Mann=7,-1,0
  4447.7    0.05       0  4604.6    0.12       0  4635.7    0.05       0
  4911.2    0.12       0  4991.1    0.07       0  4995.2    0.12       0
  5193.4    0.05       0
Bank Sta=4991.1,4995.2
Exp/Cntr=0.3,0.1

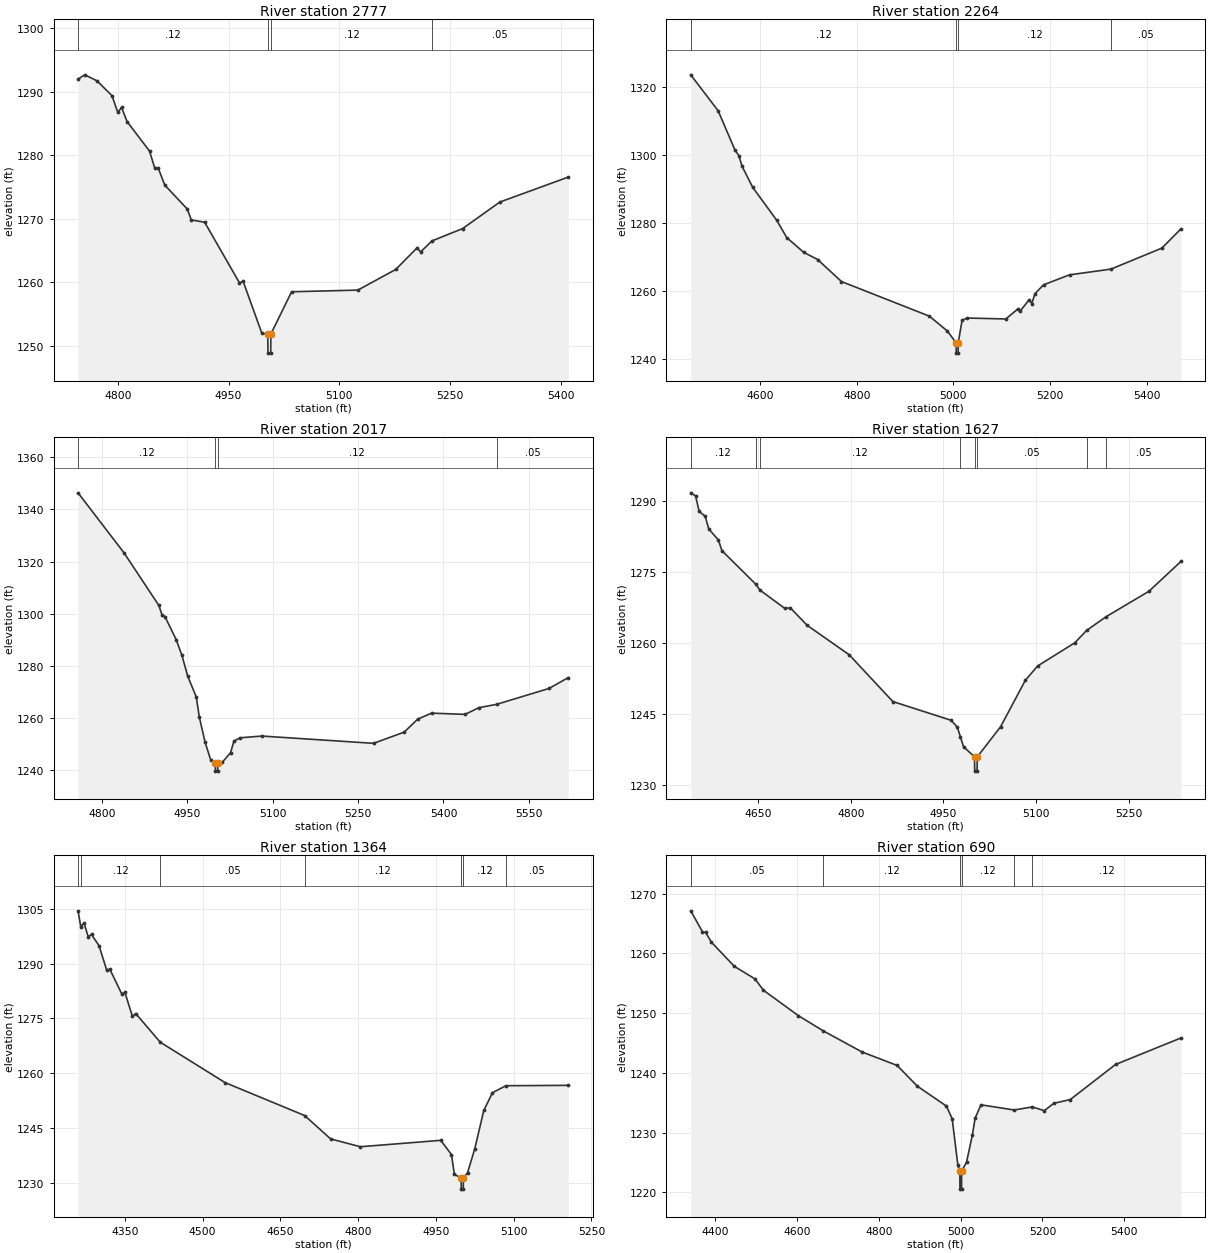
Type RM Length L Ch R = 1,2777,513,513,513
BEGIN DESCRIPTION:
SANDY 24 6.0
END DESCRIPTION:
XS GIS Cut Line= 3
      2818390.65     10182786.44      2818224.82     10182821.33
      2817733.68     10182883.33
#Sta/Elev= 30
  4745.9 1291.98  4755.0 1292.65  4771.4 1291.72  4791.9 1289.37  4799.8 1286.72
  4804.9 1287.52  4812.3 1285.30  4842.9 1280.63  4849.6 1278.06  4854.7 1277.93
  4863.4 1275.30  4894.0 1271.52  4899.4 1269.81  4917.5 1269.45  4964.7 1259.91
  4969.7 1260.14  4995.1 1251.96  5003.1 1251.84  5003.4 1248.84  5007.1 1248.84
  5007.3 1251.84  5035.4 1258.50  5125.2 1258.76  5176.6 1262.01  5205.4 1265.40
  5210.4 1264.78  5225.8 1266.51  5267.3 1268.45  5317.7 1272.62  5410.4 1276.55
#Mann=4,-1,0
  4745.9    0.12       0  5003.1    0.07       0  5007.3    0.12       0
  5225.8    0.05       0
Bank Sta=5003.1,5007.3
Exp/Cntr=0.3,0.1

Type RM Length L Ch R = 1,2264,247,247,247
BEGIN DESCRIPTION:
SANDY 24 5.0
END DESCRIPTION:
XS GIS Cut Line= 4
      2818305.66     10182153.13      2817924.69     10182464.92
      2817804.89     10182480.55      2817655.60     10182853.79
#Sta/Elev= 30
  4456.0 1323.51  4512.7 1312.97  4547.8 1301.38  4555.7 1299.80  4562.2 1296.69
  4584.5 1290.45  4634.0 1280.85  4654.8 1275.75  4690.0 1271.42  4718.7 1269.32
  4768.2 1262.85  4950.3 1252.69  4987.6 1248.32  5005.6 1244.85  5005.9 1241.85
  5009.7 1241.85  5009.9 1244.85  5017.9 1251.45  5028.0 1252.15  5108.5 1251.87
  5132.7 1254.72  5138.1 1254.17  5156.9 1257.52  5162.3 1256.39  5168.8 1259.27
  5186.6 1261.89  5240.4 1264.82  5326.2 1266.50  5431.6 1272.66  5471.1 1278.30
#Mann=4,-1,0
  4456.0    0.12       0  5005.6    0.07       0  5009.9    0.12       0
  5326.2    0.05       0
Bank Sta=5005.6,5009.9
Exp/Cntr=0.3,0.1

Type RM Length L Ch R = 1,2017,390,390,390
BEGIN DESCRIPTION:
SANDY 24 4.0
END DESCRIPTION:
XS GIS Cut Line= 3
      2817855.68     10182003.14      2817791.01     10182381.59
      2817612.18     10182824.30
#Sta/Elev= 30
  4757.8 1346.31  4838.9 1323.23  4899.8 1303.17  4905.5 1299.46  4910.6 1298.88
  4930.2 1290.09  4940.4 1283.99  4950.5 1276.08  4965.6 1268.08  4970.8 1260.56
  4981.0 1250.77  4991.1 1243.87  4999.0 1242.69  4999.3 1239.69  5003.1 1239.69
  5003.4 1242.69  5011.4 1243.10  5025.8 1246.75  5031.7 1251.13  5041.8 1252.44
  5080.8 1253.13  5277.1 1250.34  5330.8 1254.62  5354.9 1259.63  5379.1 1261.90
  5438.1 1261.44  5462.3 1264.01  5493.3 1265.27  5585.6 1271.37  5619.2 1275.51
#Mann=4,-1,0
  4757.8    0.12       0  4999.0    0.07       0  5003.4    0.12       0
  5493.3    0.05       0
Bank Sta=4999,5003.4
Exp/Cntr=0.3,0.1

Type RM Length L Ch R = 1,1627,263,263,263
BEGIN DESCRIPTION:
SANDY 24 3.0
END DESCRIPTION:
XS GIS Cut Line= 3
      2817705.70     10182053.08      2817521.49     10182358.89
      2817511.49     10182794.77
#Sta/Elev= 30
  4541.2 1291.71  4549.0 1291.07  4554.8 1287.78  4564.5 1286.78  4570.4 1284.08
  4585.9 1281.75  4591.7 1279.48  4646.0 1272.47  4652.9 1271.19  4693.0 1267.34
  4702.4 1267.40  4729.6 1263.72  4797.5 1257.51  4868.1 1247.63  4962.4 1243.67
  4972.4 1242.25  4977.4 1240.20  4982.5 1238.10  5000.3 1235.93  5000.6 1232.93
  5004.4 1232.93  5004.7 1235.93  5042.5 1242.31  5082.5 1252.11  5102.5 1255.15
  5162.5 1260.03  5181.7 1262.65  5212.9 1265.52  5282.5 1270.92  5334.2 1277.21
#Mann=8,-1,0
  4541.2    0.12       0  4646.0    0.05       0  4652.9    0.12       0
  4977.4    0.05       0  5000.3    0.03       0  5004.7    0.05       0
  5181.7    0.12       0  5212.9    0.05       0
Bank Sta=5000.3,5004.7
Exp/Cntr=0.3,0.1

Type RM Length L Ch R = 1,1364,674,674,674
BEGIN DESCRIPTION:
SANDY 24 2.0
END DESCRIPTION:
XS GIS Cut Line= 3
      2817723.29     10181853.82      2817334.41     10182150.68
      2817211.63     10182589.90
#Sta/Elev= 30
  4259.8 1304.42  4265.0 1300.10  4271.3 1301.07  4279.5 1297.30  4285.8 1297.95
  4300.3 1294.86  4314.9 1288.26  4321.2 1288.41  4343.9 1281.74  4350.2 1282.07
  4364.7 1275.52  4371.0 1276.32  4418.3 1268.47  4543.4 1257.41  4696.9 1248.39
  4746.9 1242.00  4804.3 1239.86  4959.2 1241.61  4980.0 1237.72  4985.5 1232.34
  4998.6 1231.26  4998.9 1228.26  5002.7 1228.26  5003.0 1231.26  5011.1 1232.81
  5024.8 1239.24  5042.3 1249.78  5059.0 1254.64  5084.9 1256.56  5205.1 1256.66
#Mann=7,-1,0
  4259.8    0.05       0  4265.0    0.12       0  4418.3    0.05       0
  4696.9    0.12       0  4998.6    0.07       0  5003.0    0.12       0
  5084.9    0.05       0
Bank Sta=4998.6,5003
Exp/Cntr=0.3,0.1

Type RM Length L Ch R = 1,690,0,0,0
BEGIN DESCRIPTION:
SANDY 24 1.0
END DESCRIPTION:
XS GIS Cut Line= 3
      2817468.09     10181334.72      2816931.63     10181940.61
      2817030.59     10182315.62
#Sta/Elev= 30
  4341.0 1267.13  4369.7 1263.61  4377.3 1263.53  4391.5 1261.87  4447.5 1257.83
  4497.7 1255.74  4518.6 1253.83  4604.0 1249.57  4665.1 1247.01  4759.5 1243.49
  4844.8 1241.25  4894.2 1237.78  4965.3 1234.44  4979.5 1232.31  4993.3 1224.59
  4998.2 1223.53  4998.5 1220.53  5002.3 1220.53  5002.6 1223.53  5014.6 1225.06
  5028.9 1229.62  5035.5 1232.40  5049.8 1234.65  5130.9 1233.78  5174.9 1234.29
  5204.6 1233.67  5227.7 1234.90  5267.9 1235.53  5378.4 1241.40  5538.1 1245.84
#Mann=6,-1,0
  4341.0    0.05       0  4665.1    0.12       0  4998.2    0.07       0
  5002.6    0.12       0  5130.9    0.05       0  5174.9    0.12       0
Bank Sta=4998.2,5002.6
Exp/Cntr=0.3,0.1

Chan Stop Cuts=-1