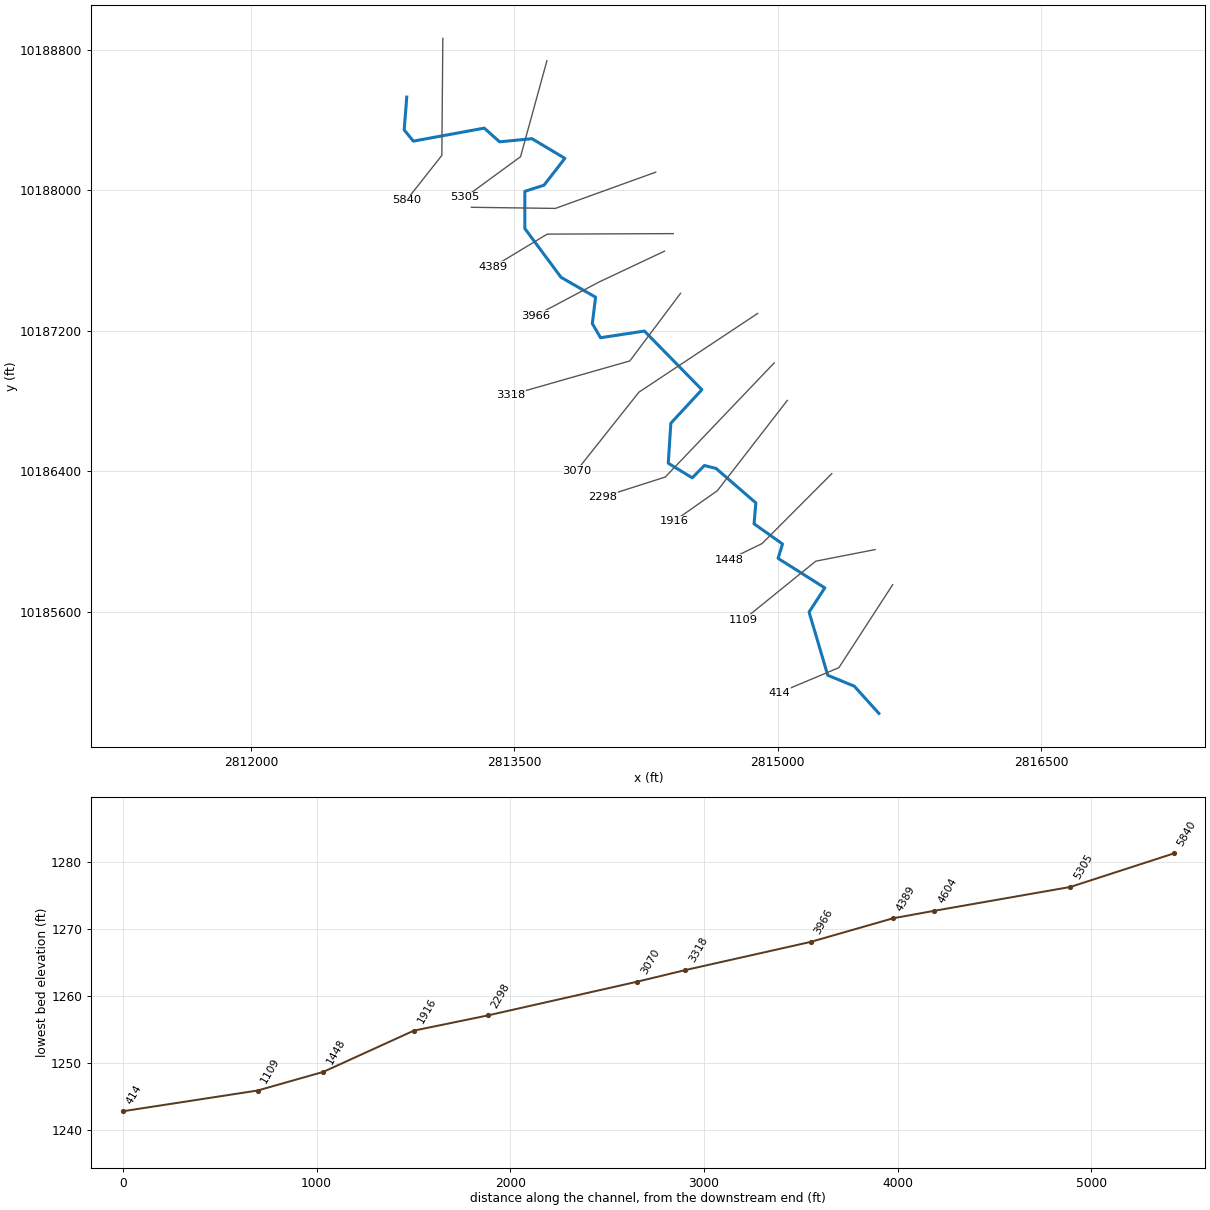
--- SANDY 26.prj (project) ---

Proj Title=SANDY 26 Base Level Engineering
Current Plan=p01
Default Exp/Contr=0.3,0.1
English Units
Geom File=g01
Flow File=f01
Plan File=p01
BEGIN DESCRIPTION:
SANDY 26
END DESCRIPTION:

--- SANDY 26.p01 (plan) ---

Plan Title=Multiple Run
Short Identifier=Multiple
Geom File=g01
Flow File=f01
Subcritical Flow
K Sum by GR= 0
Std Step Tol= 0.01
Critical Tol= 0.01
Num of Std Step Trials= 20
Max Error Tol= 0.3
Flow Tol Ratio= 0.001
Split Flow NTrial= 30
Split Flow Tol= 0.02
Split Flow Ratio= 0.02
Log Output Level= 0
Friction Slope Method= 1
Unsteady Friction Slope Method= 2
Unsteady Bridges Friction Slope Method= 1
Parabolic Critical Depth
Global Vel Dist=  1 , 1 , 1
Global Log Level= 0
CheckData=True
Encroach Param= -1, 0, 0, 0
BEGIN DESCRIPTION:
Multiple Run
END DESCRIPTION:

--- SANDY 26.f01 (steady flow) ---

Flow Title=Multiple
Number of Profiles=7
Profile Names=10-year,25-year,50-year,1pct_min,100-year,1pct_plu,500-year
River Rch & RM= SANDY 26,Reach-1,5840
      82     163     258     135     409    1235    1099
Boundary for River Rch & Prof#=SANDY 26,Reach-1,1
Up Type=0
Dn Type=3
Dn Slope=0.005
Boundary for River Rch & Prof#=SANDY 26,Reach-1,2
Up Type=0
Dn Type=3
Dn Slope=0.005
Boundary for River Rch & Prof#=SANDY 26,Reach-1,3
Up Type=0
Dn Type=3
Dn Slope=0.005
Boundary for River Rch & Prof#=SANDY 26,Reach-1,4
Up Type=0
Dn Type=3
Dn Slope=0.005
Boundary for River Rch & Prof#=SANDY 26,Reach-1,5
Up Type=0
Dn Type=3
Dn Slope=0.005
Boundary for River Rch & Prof#=SANDY 26,Reach-1,6
Up Type=0
Dn Type=3
Dn Slope=0.005
Boundary for River Rch & Prof#=SANDY 26,Reach-1,7
Up Type=0
Dn Type=3
Dn Slope=0.005

--- SANDY 26.g01 (geometry) ---

Geom Title=Existing Conditions

River Reach=SANDY 26,Reach-1
Reach XY= 30
      2812887.50     10188531.00      2812872.75     10188344.00
      2812925.00     10188280.00      2813329.00     10188354.00
      2813416.50     10188276.00      2813600.75     10188294.00
      2813788.25     10188182.00      2813669.50     10188029.00
      2813560.25     10187994.00      2813560.25     10187782.00
      2813766.50     10187504.00      2813963.25     10187391.00
      2813944.50     10187241.00      2813991.50     10187160.00
      2814241.50     10187198.00      2814568.75     10186864.00
      2814392.00     10186673.00      2814377.25     10186445.00
      2814514.00     10186362.00      2814583.25     10186432.00
      2814650.00     10186415.00      2814876.25     10186219.00
      2814866.00     10186100.00      2815028.25     10185985.00
      2815003.00     10185903.00      2815269.00     10185735.00
      2815179.50     10185597.00      2815286.00     10185237.00
      2815437.00     10185175.00      2815577.00     10185020.00

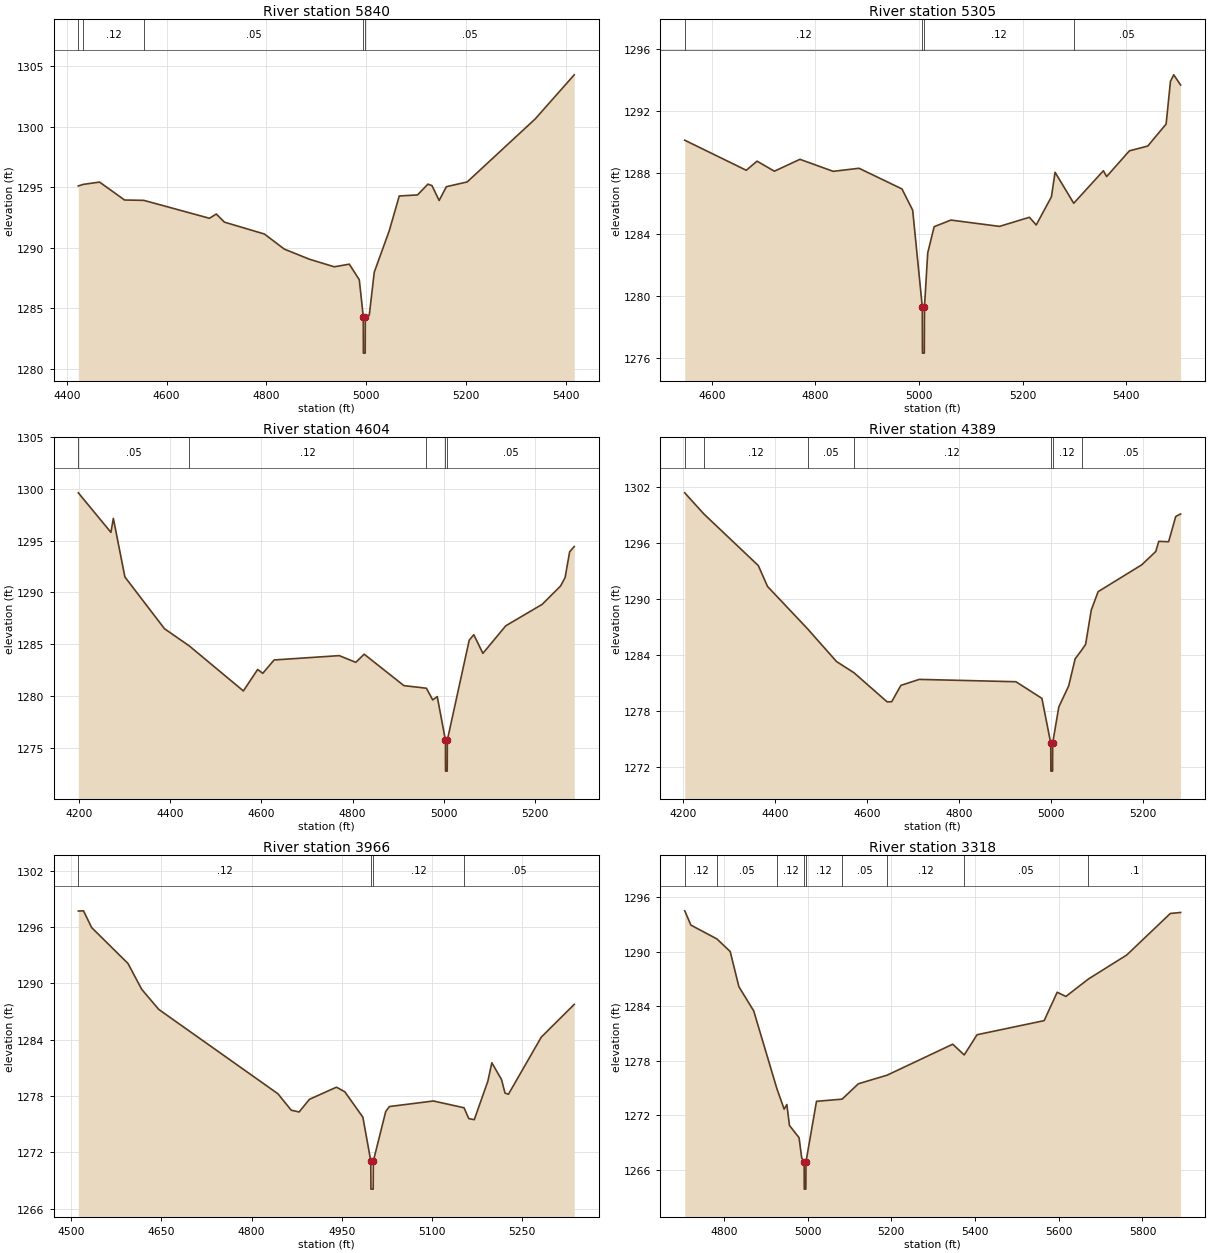
Type RM Length L Ch R = 1,5840,535,535,535
BEGIN DESCRIPTION:
SANDY 26 12.0
END DESCRIPTION:
XS GIS Cut Line= 3
      2813092.98     10188865.61      2813087.42     10188198.65
      2812885.47     10187942.97
#Sta/Elev= 30
  4423.3 1295.11  4433.2 1295.24  4465.8 1295.43  4515.8 1293.95  4554.4 1293.92
  4685.8 1292.44  4699.5 1292.79  4715.8 1292.12  4795.8 1291.14  4835.8 1289.89
  4885.8 1289.06  4935.8 1288.43  4965.8 1288.65  4985.8 1287.36  4993.8 1284.30
  4994.0 1281.30  4997.6 1281.30  4997.9 1284.30  5005.8 1284.44  5015.8 1287.99
  5045.8 1291.41  5065.8 1294.28  5102.4 1294.37  5123.2 1295.26  5131.3 1295.14
  5145.7 1293.91  5160.2 1295.05  5201.8 1295.44  5338.1 1300.65  5416.1 1304.29
#Mann=5,-1,0
  4423.3    0.05       0  4433.2    0.12       0  4554.4    0.05       0
  4993.8    0.05       0  4997.9    0.05       0
Bank Sta=4993.8,4997.9
Exp/Cntr=0.3,0.1

Type RM Length L Ch R = 1,5305,701,701,701
BEGIN DESCRIPTION:
SANDY 26 11.0
END DESCRIPTION:
XS GIS Cut Line= 3
      2813685.83     10188737.79      2813535.76     10188191.24
      2813219.85     10187960.30
#Sta/Elev= 30
  4547.4 1290.10  4666.3 1288.15  4687.1 1288.74  4720.6 1288.09  4770.0 1288.86
  4834.3 1288.08  4884.1 1288.28  4967.1 1286.94  4987.8 1285.56  5006.4 1279.29
  5006.7 1276.29  5010.3 1276.29  5010.6 1279.29  5016.9 1282.79  5029.3 1284.49
  5061.7 1284.92  5155.5 1284.51  5213.4 1285.10  5226.5 1284.60  5255.9 1286.43
  5262.9 1288.02  5299.0 1286.01  5356.3 1288.12  5362.5 1287.74  5406.5 1289.41
  5442.0 1289.72  5477.5 1291.15  5485.9 1293.92  5492.2 1294.34  5505.5 1293.68
#Mann=4,-1,0
  4547.4    0.12       0  5006.4    0.07       0  5010.6    0.12       0
  5299.0    0.05       0
Bank Sta=5006.4,5010.6
Exp/Cntr=0.3,0.1

Type RM Length L Ch R = 1,4604,215,215,215
BEGIN DESCRIPTION:
SANDY 26 10.0
END DESCRIPTION:
XS GIS Cut Line= 3
      2814305.69     10188103.11      2813734.00     10187896.66
      2813255.67     10187903.11
#Sta/Elev= 30
  4199.2 1299.63  4270.6 1295.81  4275.9 1297.16  4301.2 1291.50  4387.9 1286.50
  4441.9 1284.85  4560.7 1280.49  4592.0 1282.56  4603.2 1282.19  4628.0 1283.48
  4770.7 1283.90  4807.0 1283.25  4825.3 1284.04  4912.4 1281.00  4961.7 1280.75
  4975.4 1279.62  4985.4 1279.94  5003.3 1275.74  5003.5 1272.74  5007.2 1272.74
  5007.5 1275.74  5055.4 1285.39  5065.4 1285.92  5085.4 1284.12  5135.4 1286.78
  5215.4 1288.86  5255.4 1290.62  5265.4 1291.44  5275.4 1293.93  5285.4 1294.44
#Mann=5,-1,0
  4199.2    0.05       0  4441.9    0.12       0  4961.7    0.05       0
  5003.3    0.05       0  5007.5    0.05       0
Bank Sta=5003.3,5007.5
Exp/Cntr=0.3,0.1

Type RM Length L Ch R = 1,4389,423,423,423
BEGIN DESCRIPTION:
SANDY 26 9.0
END DESCRIPTION:
XS GIS Cut Line= 3
      2814405.67     10187753.11      2813687.68     10187750.30
      2813379.46     10187563.89
#Sta/Elev= 30
  4203.0 1301.37  4244.6 1299.11  4363.0 1293.59  4383.0 1291.36  4470.2 1286.82
  4533.0 1283.33  4571.0 1282.13  4643.0 1279.02  4653.0 1279.03  4673.0 1280.78
  4713.0 1281.42  4923.1 1281.17  4979.6 1279.39  4998.8 1274.61  4999.1 1271.61
  5002.8 1271.61  5003.0 1274.61  5016.4 1278.48  5037.8 1280.72  5051.9 1283.62
  5066.5 1284.58  5074.6 1285.16  5086.9 1288.83  5101.8 1290.80  5196.9 1293.68
  5227.2 1295.10  5233.7 1296.18  5255.1 1296.14  5270.6 1298.84  5281.2 1299.11
#Mann=7,-1,0
  4203.0    0.05       0  4244.6    0.12       0  4470.2    0.05       0
  4571.0    0.12       0  4998.8    0.07       0  5003.0    0.12       0
  5066.5    0.05       0
Bank Sta=4998.8,5003
Exp/Cntr=0.3,0.1

Type RM Length L Ch R = 1,3966,648,648,648
BEGIN DESCRIPTION:
SANDY 26 8.0
END DESCRIPTION:
XS GIS Cut Line= 3
      2814355.68     10187653.11      2813980.40     10187476.11
      2813618.96     10187284.32
#Sta/Elev= 30
  4512.2 1297.70  4520.8 1297.72  4534.3 1295.94  4594.7 1292.12  4617.5 1289.37
  4645.8 1287.23  4843.9 1278.25  4866.0 1276.50  4879.1 1276.31  4896.3 1277.66
  4941.2 1278.95  4955.1 1278.46  4985.1 1275.75  4998.2 1271.10  4998.5 1268.10
  5002.2 1268.10  5002.5 1271.10  5023.0 1276.35  5029.1 1276.89  5102.3 1277.48
  5153.2 1276.76  5161.0 1275.61  5170.2 1275.49  5192.8 1279.59  5199.4 1281.55
  5215.5 1279.76  5221.3 1278.32  5227.0 1278.20  5281.6 1284.28  5336.3 1287.76
#Mann=4,-1,0
  4512.2    0.12       0  4998.2    0.07       0  5002.5    0.12       0
  5153.2    0.05       0
Bank Sta=4998.2,5002.5
Exp/Cntr=0.3,0.1

Type RM Length L Ch R = 1,3318,248,248,248
BEGIN DESCRIPTION:
SANDY 26 7.0
END DESCRIPTION:
XS GIS Cut Line= 3
      2814447.25     10187413.09      2814158.26     10187027.76
      2813482.03     10186835.08
#Sta/Elev= 30
  4706.4 1294.48  4721.2 1292.91  4783.3 1291.39  4815.0 1290.01  4835.8 1286.14
  4871.2 1283.48  4926.4 1274.96  4943.9 1272.68  4950.4 1273.19  4956.6 1270.89
  4979.6 1269.54  4985.8 1267.34  4991.7 1266.89  4992.0 1263.89  4995.8 1263.89
  4996.1 1266.89  5021.2 1273.54  5082.4 1273.78  5121.2 1275.47  5190.2 1276.42
  5346.7 1279.82  5374.2 1278.64  5404.8 1280.86  5565.1 1282.41  5596.3 1285.53
  5617.1 1285.07  5670.4 1286.97  5762.6 1289.63  5866.6 1294.19  5891.2 1294.30
#Mann=9,-1,0
  4706.4    0.12       0  4783.3    0.05       0  4926.4    0.12       0
  4991.7    0.07       0  4996.1    0.12       0  5082.4    0.05       0
  5190.2    0.12       0  5374.2    0.05       0  5670.4     0.1       0
Bank Sta=4991.7,4996.1
Exp/Cntr=0.3,0.1

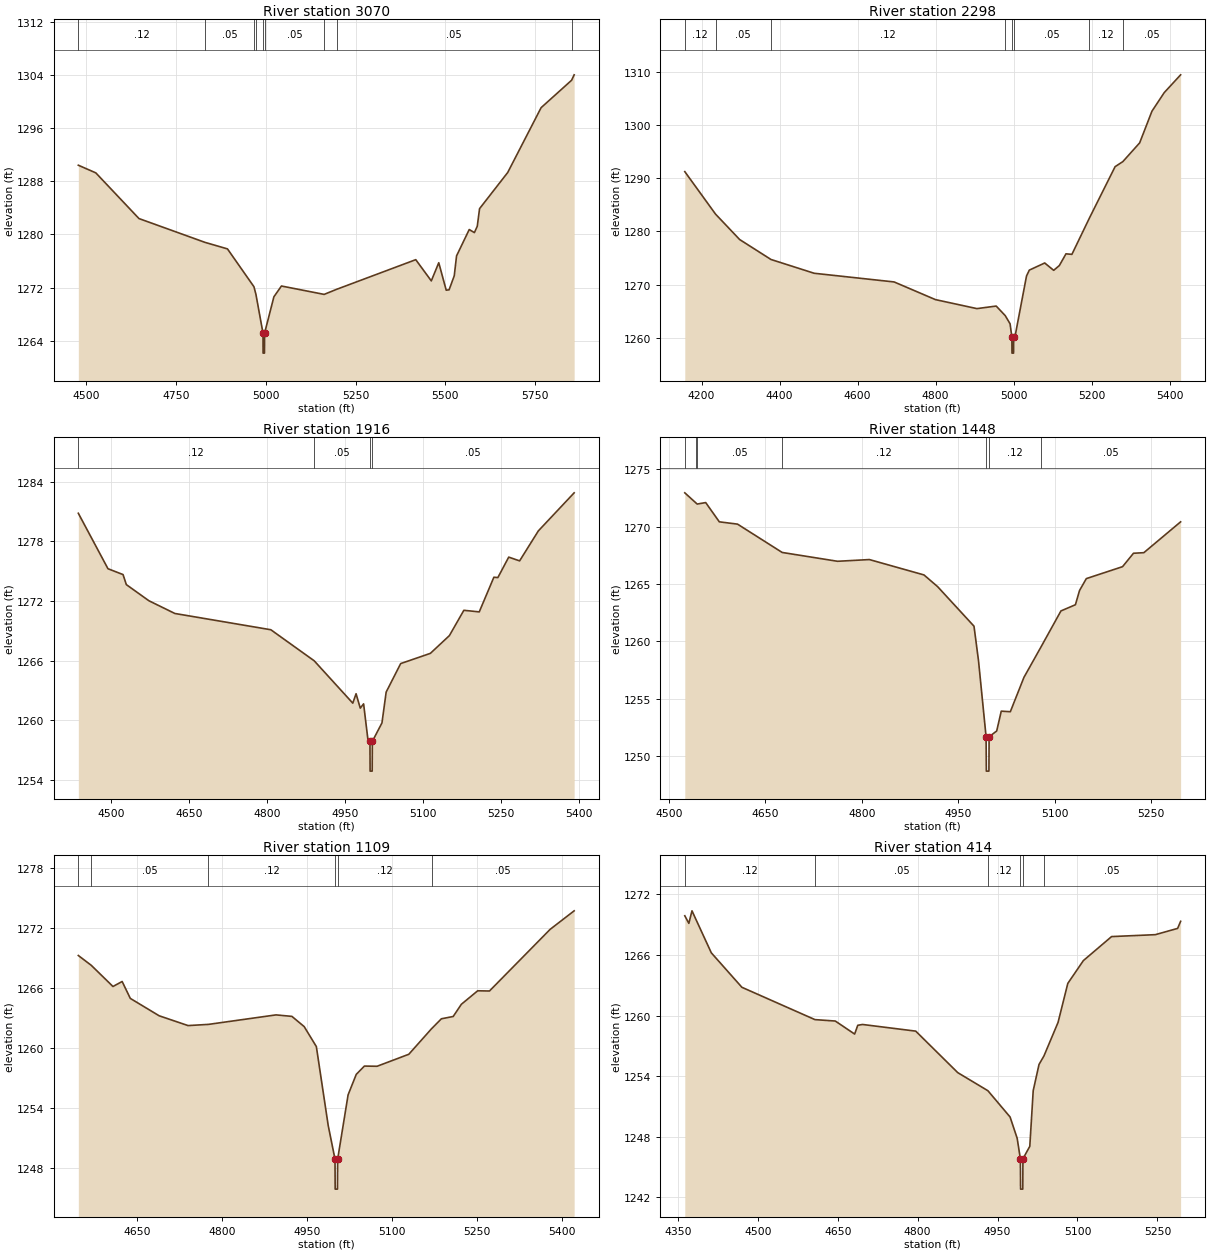
Type RM Length L Ch R = 1,3070,772,772,772
BEGIN DESCRIPTION:
SANDY 26 6.0
END DESCRIPTION:
XS GIS Cut Line= 3
      2814886.39     10187298.27      2814210.13     10186849.91
      2813855.69     10186403.12
#Sta/Elev= 30
  4477.5 1290.41  4526.2 1289.26  4646.5 1282.39  4830.6 1278.81  4893.1 1277.83
  4966.9 1272.14  4972.4 1271.00  4992.1 1265.16  4992.4 1262.16  4996.2 1262.16
  4996.5 1265.16  5022.5 1270.63  5043.5 1272.25  5162.5 1270.99  5197.2 1271.75
  5417.8 1276.21  5461.1 1273.02  5481.9 1275.75  5502.7 1271.62  5510.7 1271.68
  5525.1 1273.79  5531.5 1276.78  5566.8 1280.74  5581.2 1280.28  5589.2 1281.23
  5595.6 1283.88  5674.1 1289.32  5767.1 1299.06  5852.0 1303.18  5859.2 1304.00
#Mann=9,-1,0
  4477.5    0.12       0  4830.6    0.05       0  4966.9    0.12       0
  4972.4    0.05       0  4992.1    0.05       0  4996.5    0.05       0
  5162.5    0.12       0  5197.2    0.05       0  5852.0    0.12       0
Bank Sta=4992.1,4996.5
Exp/Cntr=0.3,0.1

Type RM Length L Ch R = 1,2298,382,382,382
BEGIN DESCRIPTION:
SANDY 26 5.0
END DESCRIPTION:
XS GIS Cut Line= 3
      2814980.86     10187016.66      2814360.20     10186366.36
      2814005.70     10186253.12
#Sta/Elev= 30
  4157.0 1291.21  4235.8 1283.23  4297.7 1278.45  4377.9 1274.71  4488.6 1272.12
  4693.6 1270.49  4799.6 1267.17  4905.9 1265.48  4955.3 1265.96  4978.4 1264.17
  4990.9 1262.63  4995.5 1260.12  4995.8 1257.12  4999.8 1257.12  5000.1 1260.12
  5005.0 1260.80  5033.0 1271.60  5040.2 1272.71  5079.7 1274.05  5102.7 1272.67
  5117.2 1273.57  5134.2 1275.77  5149.4 1275.67  5193.7 1282.40  5260.1 1292.14
  5280.0 1293.09  5323.1 1296.61  5354.6 1302.56  5386.1 1306.05  5428.1 1309.39
#Mann=8,-1,0
  4157.0    0.12       0  4235.8    0.05       0  4377.9    0.12       0
  4978.4    0.05       0  4995.5    0.05       0  5000.1    0.05       0
  5193.7    0.12       0  5280.0    0.05       0
Bank Sta=4995.5,5000.1
Exp/Cntr=0.3,0.1

Type RM Length L Ch R = 1,1916,468,468,468
BEGIN DESCRIPTION:
SANDY 26 4.0
END DESCRIPTION:
XS GIS Cut Line= 3
      2815055.67     10186803.09      2814656.59     10186288.20
      2814409.32     10186114.72
#Sta/Elev= 30
  4437.4 1280.84  4494.4 1275.25  4523.4 1274.66  4529.7 1273.65  4573.2 1272.02
  4623.0 1270.74  4807.6 1269.10  4891.0 1265.97  4965.2 1261.70  4971.5 1262.65
  4979.6 1261.20  4986.0 1261.63  4994.1 1258.12  4998.2 1257.85  4998.5 1254.85
  5002.5 1254.85  5002.8 1257.85  5021.3 1259.71  5029.4 1262.82  5057.3 1265.69
  5114.4 1266.72  5151.0 1268.51  5178.8 1271.06  5208.4 1270.90  5236.5 1274.39
  5244.2 1274.36  5265.1 1276.42  5286.0 1276.04  5322.0 1279.06  5390.9 1282.90
#Mann=4,-1,0
  4437.4    0.12       0  4891.0    0.05       0  4998.2    0.05       0
  5002.8    0.05       0
Bank Sta=4998.2,5002.8
Exp/Cntr=0.3,0.1

Type RM Length L Ch R = 1,1448,339,339,339
BEGIN DESCRIPTION:
SANDY 26 3.0
END DESCRIPTION:
XS GIS Cut Line= 3
      2815308.89     10186385.82      2814911.79     10185987.42
      2814724.28     10185896.26
#Sta/Elev= 30
  4524.9 1272.96  4542.2 1272.08  4544.2 1271.98  4557.4 1272.11  4578.6 1270.43
  4606.9 1270.23  4676.3 1267.76  4762.4 1266.99  4811.9 1267.14  4896.8 1265.80
  4918.0 1264.78  4974.6 1261.33  4981.6 1258.33  4993.4 1251.69  4993.8 1248.69
  4997.8 1248.69  4998.1 1251.69  5009.9 1252.19  5017.0 1253.92  5031.1 1253.87
  5052.3 1256.87  5078.4 1259.48  5109.8 1262.66  5132.3 1263.20  5138.7 1264.44
  5149.3 1265.48  5205.6 1266.52  5222.6 1267.69  5238.7 1267.74  5295.9 1270.43
#Mann=7,-1,0
  4524.9    0.05       0  4542.2    0.12       0  4544.2    0.05       0
  4676.3    0.12       0  4993.4    0.07       0  4998.1    0.12       0
  5078.4    0.05       0
Bank Sta=4993.4,4998.1
Exp/Cntr=0.3,0.1

Type RM Length L Ch R = 1,1109,695,695,695
BEGIN DESCRIPTION:
SANDY 26 2.0
END DESCRIPTION:
XS GIS Cut Line= 3
      2815555.66     10185953.11      2815217.78     10185887.16
      2814805.71     10185553.13
#Sta/Elev= 30
  4546.3 1269.28  4569.1 1268.30  4607.4 1266.18  4623.6 1266.68  4638.0 1264.99
  4688.9 1263.25  4739.9 1262.27  4775.9 1262.39  4895.1 1263.34  4923.1 1263.19
  4944.7 1262.17  4966.2 1260.17  4987.1 1252.28  4999.1 1248.91  4999.4 1245.91
  5003.4 1245.91  5003.8 1248.91  5022.2 1255.34  5036.6 1257.39  5051.0 1258.22
  5073.3 1258.20  5129.3 1259.40  5169.5 1261.96  5186.8 1262.95  5207.6 1263.18
  5222.0 1264.40  5250.8 1265.75  5271.6 1265.73  5378.7 1271.90  5421.0 1273.75
#Mann=6,-1,0
  4546.3    0.12       0  4569.1    0.05       0  4775.9    0.12       0
  4999.1    0.07       0  5003.8    0.12       0  5169.5    0.05       0
Bank Sta=4999.1,5003.8
Exp/Cntr=0.3,0.1

Type RM Length L Ch R = 1,414,0,0,0
BEGIN DESCRIPTION:
SANDY 26 1.0
END DESCRIPTION:
XS GIS Cut Line= 3
      2815655.68     10185753.11      2815349.29     10185280.38
      2815010.57     10185138.17
#Sta/Elev= 30
  4362.9 1269.88  4370.5 1269.13  4376.4 1270.37  4412.7 1266.21  4470.1 1262.80
  4607.2 1259.60  4645.4 1259.46  4681.7 1258.17  4687.6 1259.04  4696.6 1259.12
  4796.4 1258.46  4875.3 1254.35  4931.9 1252.56  4973.5 1249.96  4986.8 1247.85
  4992.8 1245.82  4993.2 1242.82  4997.3 1242.82  4997.6 1245.82  5010.5 1247.06
  5016.9 1252.57  5027.8 1255.16  5037.1 1256.01  5063.5 1259.32  5081.8 1263.18
  5111.0 1265.44  5164.0 1267.82  5246.1 1268.01  5288.0 1268.63  5293.6 1269.33
#Mann=6,-1,0
  4362.9    0.12       0  4607.2    0.05       0  4931.9    0.12       0
  4992.8    0.07       0  4997.6    0.12       0  5037.1    0.05       0
Bank Sta=4992.8,4997.6
Exp/Cntr=0.3,0.1

Chan Stop Cuts=-1