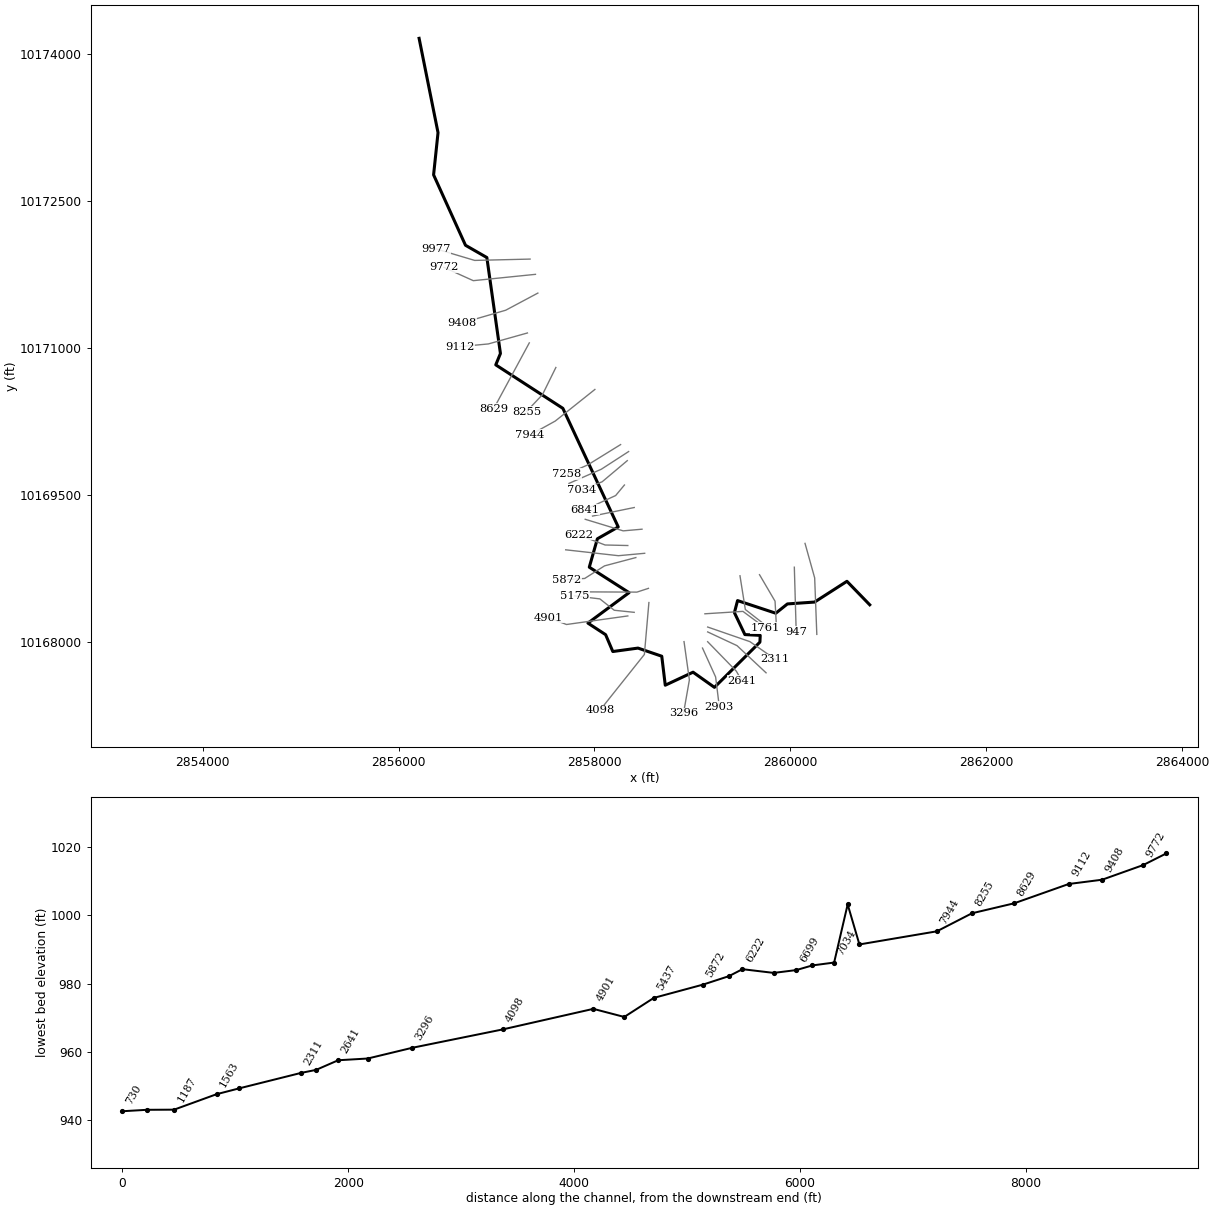
--- SANDY 30.prj (project) ---

Proj Title=SANDY 30 Base Level Engineering
Current Plan=p01
Default Exp/Contr=0.3,0.1
English Units
Geom File=g01
Flow File=f01
Plan File=p01
Y Axis Title=Elevation
X Axis Title(PF)=Main Channel Distance
X Axis Title(XS)=Station
BEGIN DESCRIPTION:
SANDY 30
END DESCRIPTION:
DSS Export Rating Curves= 0
DSS Export Rating Curve Sorted= 0
DSS Export Volume Flow Curves= 0
DXF OffsetX= 0
DXF OffsetY= 0
DXF ScaleX= 1
DXF ScaleY= 10

--- SANDY 30.p01 (plan) ---

Plan Title=Multiple Run
Short Identifier=Multiple
Geom File=g01
Flow File=f01
Subcritical Flow
K Sum by GR= 0
Std Step Tol= 0.01
Critical Tol= 0.01
Num of Std Step Trials= 20
Max Error Tol= 0.3
Flow Tol Ratio= 0.001
Split Flow NTrial= 30
Split Flow Tol= 0.02
Split Flow Ratio= 0.02
Log Output Level= 0
Friction Slope Method= 1
Unsteady Friction Slope Method= 2
Unsteady Bridges Friction Slope Method= 1
Parabolic Critical Depth
Global Vel Dist=  1 , 1 , 1
Global Log Level= 0
CheckData=True
Encroach Param= -1, 0, 0, 0
BEGIN DESCRIPTION:
Multiple Run
END DESCRIPTION:

--- SANDY 30.f01 (steady flow) ---

Flow Title=Multiple
Number of Profiles=7
Profile Names=10-year,25-year,50-year,1pct_min,100-year,1pct_plu,500-year
River Rch & RM= SANDY 30,Reach-1,9977
      63     120     186      96     291     878     761
Boundary for River Rch & Prof#=SANDY 30,Reach-1,1
Up Type=0
Dn Type=3
Dn Slope=0.005
Boundary for River Rch & Prof#=SANDY 30,Reach-1,2
Up Type=0
Dn Type=3
Dn Slope=0.005
Boundary for River Rch & Prof#=SANDY 30,Reach-1,3
Up Type=0
Dn Type=3
Dn Slope=0.005
Boundary for River Rch & Prof#=SANDY 30,Reach-1,4
Up Type=0
Dn Type=3
Dn Slope=0.005
Boundary for River Rch & Prof#=SANDY 30,Reach-1,5
Up Type=0
Dn Type=3
Dn Slope=0.005
Boundary for River Rch & Prof#=SANDY 30,Reach-1,6
Up Type=0
Dn Type=3
Dn Slope=0.005
Boundary for River Rch & Prof#=SANDY 30,Reach-1,7
Up Type=0
Dn Type=3
Dn Slope=0.005

--- SANDY 30.g01 (geometry) ---

Geom Title=Existing Conditions
Program Version=4.10

River Reach=SANDY 30        ,Reach-1
Reach XY= 30
      2856209.25       10174164.       2856402.5       10173201.
      2856357.25       10172770.        2856683.       10172051.
        2856901.       10171926.      2857039.75       10170946.
        2856992.       10170830.      2857677.25       10170386.
       2858242.5       10169175.       2858029.5       10169054.
        2857947.       10168764.      2858353.25       10168504.
        2857933.       10168193.      2858113.75       10168075.
      2858187.25       10167903.      2858444.25       10167938.
        2858687.       10167855.      2858722.75       10167559.
       2859006.5       10167692.        2859225.       10167537.
      2859689.25       10167999.      2859692.25       10168068.
      2859535.75       10168076.      2859428.75       10168300.
        2859461.       10168423.      2859851.25       10168294.
        2859970.       10168389.       2860247.5       10168408.
      2860577.75       10168620.       2860810.5       10168380.

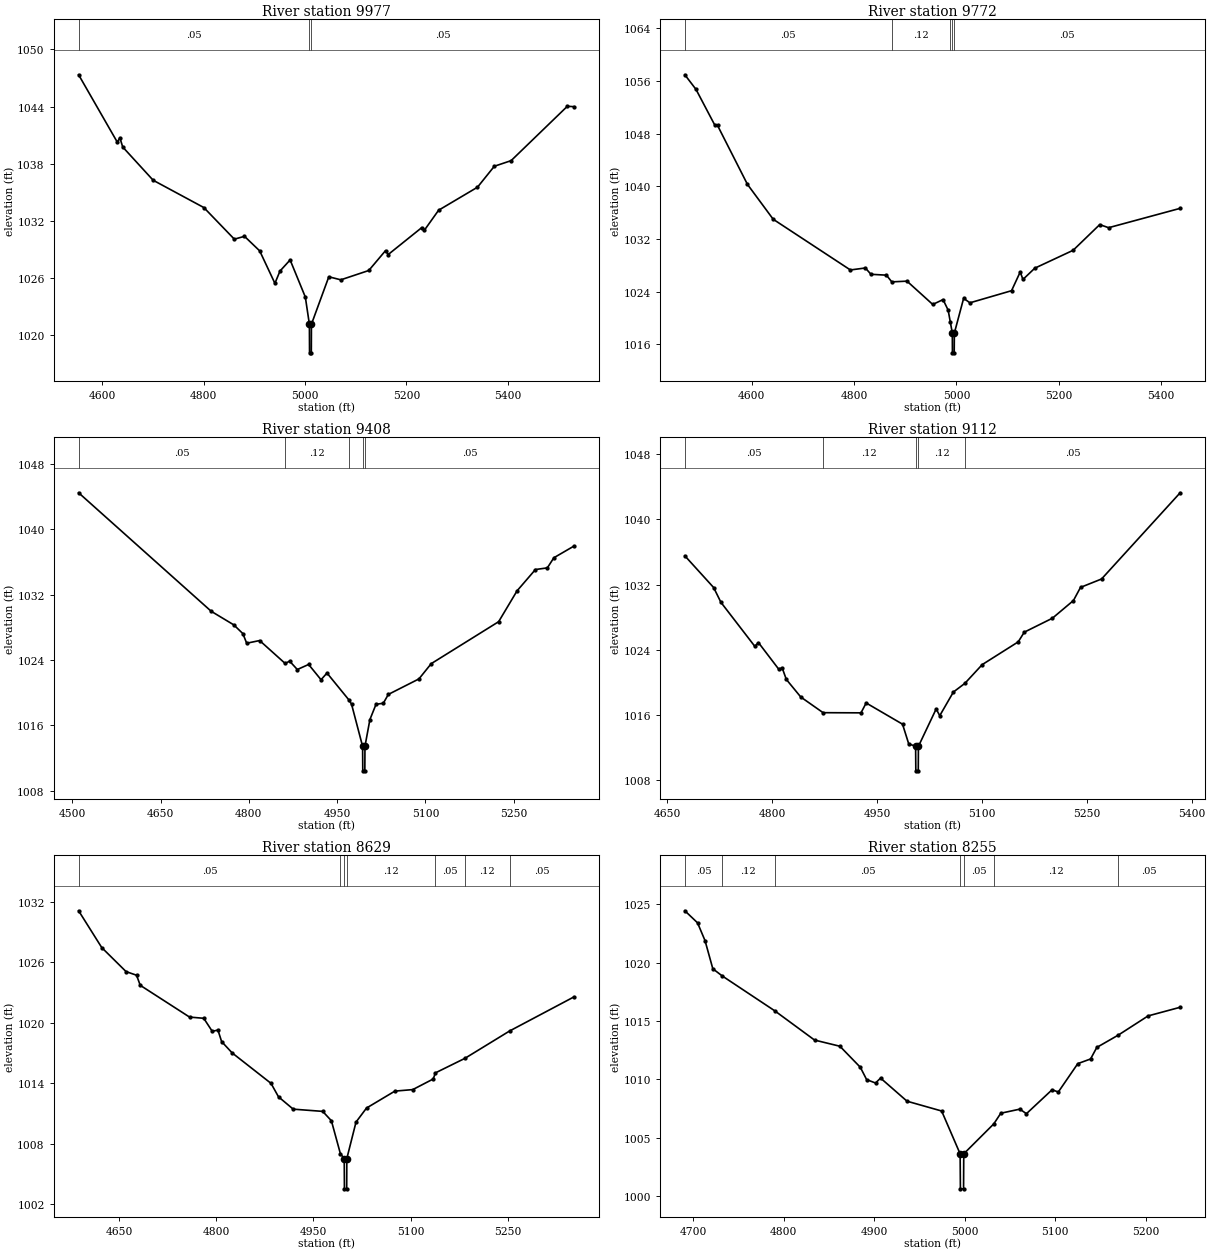
Type RM Length L Ch R = 1 ,9977    ,205,205,205
BEGIN DESCRIPTION:
SANDY 30 19.0
END DESCRIPTION:
XS GIS Cut Line= 3
      2857342.66     10171910.06      2856776.82     10171896.39
       2856383.2     10172013.93
#Sta/Elev= 30
  4553.6 1047.34  4629.9 1040.26  4634.9 1040.73  4640.6 1039.75  4700.6 1036.26
  4800.6 1033.39  4860.7 1030.07  4880.7 1030.37  4910.7 1028.84  4940.7 1025.43
  4950.7 1026.72  4970.7 1027.89  5000.7 1023.99  5008.7 1021.13    5009 1018.13
  5012.5 1018.13  5012.7 1021.13    5047 1026.12  5070.7  1025.8  5125.8 1026.78
  5158.9 1028.87  5164.2 1028.46  5230.4 1031.29  5235.6 1031.02  5263.5 1033.11
  5340.2 1035.53  5373.4 1037.73  5406.5 1038.32  5517.4 1044.03  5530.4 1043.99
#Mann= 3 ,-1 , 0
  4553.6     .05       0  5008.7     .05       0  5012.7     .05       0
Bank Sta=5008.7,5012.7
XS Rating Curve= 0 ,0
Exp/Cntr=0.3,0.1

Type RM Length L Ch R = 1 ,9772    ,364,364,364
BEGIN DESCRIPTION:
SANDY 30 18.0
END DESCRIPTION:
XS GIS Cut Line= 3
      2857397.36     10171754.25       2856762.5      10171689.6
      2856462.51     10171825.31
#Sta/Elev= 30
  4469.6 1056.96  4491.4 1054.74  4528.4 1049.27  4533.4 1049.27  4591.9 1040.31
  4642.2 1035.01  4792.9 1027.31  4822.2 1027.61  4833.1 1026.65  4863.3 1026.52
  4873.8  1025.5  4903.5 1025.61  4953.8 1022.07  4973.9 1022.81  4983.9  1021.2
    4988 1019.44    4992 1017.72  4992.2 1014.72  4995.7 1014.72    4996 1017.72
  5014.1    1023  5026.4 1022.32  5107.7 1024.16  5124.6    1027    5130 1025.87
  5153.1 1027.58    5228  1030.3  5279.9  1034.2  5297.3 1033.73    5437 1036.67
#Mann= 5 ,-1 , 0
  4469.6     .05       0  4873.8     .12       0    4988     .05       0
    4992     .05       0    4996     .05       0
Bank Sta=4992,4996
XS Rating Curve= 0 ,0
Exp/Cntr=0.3,0.1

Type RM Length L Ch R = 1 ,9408    ,296,296,296
BEGIN DESCRIPTION:
SANDY 30 17.0
END DESCRIPTION:
XS GIS Cut Line= 3
      2857421.88     10171562.89       2857093.9     10171387.97
       2856642.9     10171256.77
#Sta/Elev= 30
  4510.8 1044.49  4736.1 1029.97  4774.4 1028.31  4789.8 1027.24  4796.3 1026.06
  4818.3 1026.39  4861.7 1023.58  4869.2 1023.87  4882.3 1022.84  4901.5 1023.46
  4922.6 1021.59  4932.7 1022.41  4969.9 1019.12  4974.4  1018.6  4993.2 1013.43
  4993.5 1010.43    4997 1010.43  4997.2 1013.43  5005.6 1016.71    5016 1018.58
  5028.4 1018.71  5036.9 1019.79  5088.9 1021.69  5109.8 1023.56  5224.3  1028.7
  5255.6 1032.48  5286.8 1035.09    5307 1035.29  5318.1 1036.53  5352.2 1037.96
#Mann= 5 ,-1 , 0
  4510.8     .05       0  4861.7     .12       0  4969.9     .05       0
  4993.2     .05       0  4997.2     .05       0
Bank Sta=4993.2,4997.2
XS Rating Curve= 0 ,0
Exp/Cntr=0.3,0.1

Type RM Length L Ch R = 1 ,9112    ,483,483,483
BEGIN DESCRIPTION:
SANDY 30 16.0
END DESCRIPTION:
XS GIS Cut Line= 3
      2857315.35     10171155.63      2856916.23     10171043.55
      2856623.76     10171016.22
#Sta/Elev= 30
  4675.2 1035.54  4716.4 1031.65  4726.8 1029.84  4775.3 1024.44  4780.5  1024.9
  4809.3 1021.66  4814.5 1021.78  4820.3 1020.39    4841 1018.23  4872.9 1016.31
  4927.1 1016.29  4934.5  1017.5  4986.5  1014.9  4995.3  1012.5  5005.2 1012.18
  5005.5 1009.18    5009 1009.18  5009.2 1012.18  5034.6 1016.77  5039.7 1015.94
  5059.2 1018.84  5075.6  1019.9  5100.4  1022.2  5151.9 1024.99  5160.6 1026.18
  5200.8 1027.89  5230.9 1030.06    5241 1031.67  5271.1  1032.7  5383.5 1043.27
#Mann= 5 ,-1 , 0
  4675.2     .05       0  4872.9     .12       0  5005.2     .07       0
  5009.2     .12       0  5075.6     .05       0
Bank Sta=5005.2,5009.2
XS Rating Curve= 0 ,0
Exp/Cntr=0.3,0.1

Type RM Length L Ch R = 1 ,8629    ,374,374,374
BEGIN DESCRIPTION:
Mapping XS 27ae5748
END DESCRIPTION:
XS GIS Cut Line= 2
      2857334.44     10171054.48       2856970.9     10170382.06
#Sta/Elev= 30
  4587.7  1031.1  4623.4 1027.45  4660.9 1025.07  4677.1 1024.71  4682.8 1023.71
  4758.9 1020.56  4780.8 1020.44  4793.9 1019.15  4802.7 1019.27  4808.4 1018.13
  4824.6 1017.01  4884.6 1013.99  4896.2 1012.65  4918.9 1011.43  4964.4 1011.21
  4977.8 1010.28  4991.7 1007.01  4997.6 1006.53  4997.9 1003.53  5001.4 1003.53
  5001.6 1006.53  5015.8 1010.15    5032 1011.54  5075.8 1013.22  5103.4 1013.37
  5134.9 1014.42  5138.4 1015.03  5183.9 1016.47  5252.8 1019.18  5352.1 1022.56
#Mann= 7 ,-1 , 0
  4587.7     .05       0  4991.7     .12       0  4997.6     .07       0
  5001.6     .12       0  5138.4     .05       0  5183.9     .12       0
  5252.8     .05       0
Bank Sta=4997.6,5001.6
XS Rating Curve= 0 ,0
Exp/Cntr=0.3,0.1

Type RM Length L Ch R = 1 ,8255    ,311,311,311
BEGIN DESCRIPTION:
SANDY 30 15.0
END DESCRIPTION:
XS GIS Cut Line= 3
      2857605.69     10170803.12        2857469.       10170526.
       2857305.7     10170353.13
#Sta/Elev= 30
    4691 1024.44    4705 1023.41  4713.3 1021.88  4721.9 1019.47  4732.2 1018.86
  4790.2 1015.87  4834.2 1013.36  4862.2 1012.83  4884.7 1011.03  4891.7 1009.97
  4901.5 1009.68  4907.1  1010.1  4936.3 1008.12  4974.5 1007.28  4994.9 1003.61
  4995.2 1000.61  4998.7 1000.61  4998.9 1003.61  5032.1 1006.18  5039.8 1007.09
  5060.8 1007.44  5068.1 1007.05  5096.4  1009.1  5103.3 1008.91  5124.8 1011.34
  5138.9 1011.74  5145.8 1012.73  5169.6 1013.79  5202.4 1015.43  5237.8 1016.17
#Mann= 7 ,-1 , 0
    4691     .05       0  4732.2     .12       0  4790.2     .05       0
  4994.9     .05       0  4998.9     .05       0  5032.1     .12       0
  5169.6     .05       0
Bank Sta=4994.9,4998.9
XS Rating Curve= 0 ,0
Exp/Cntr=0.3,0.1

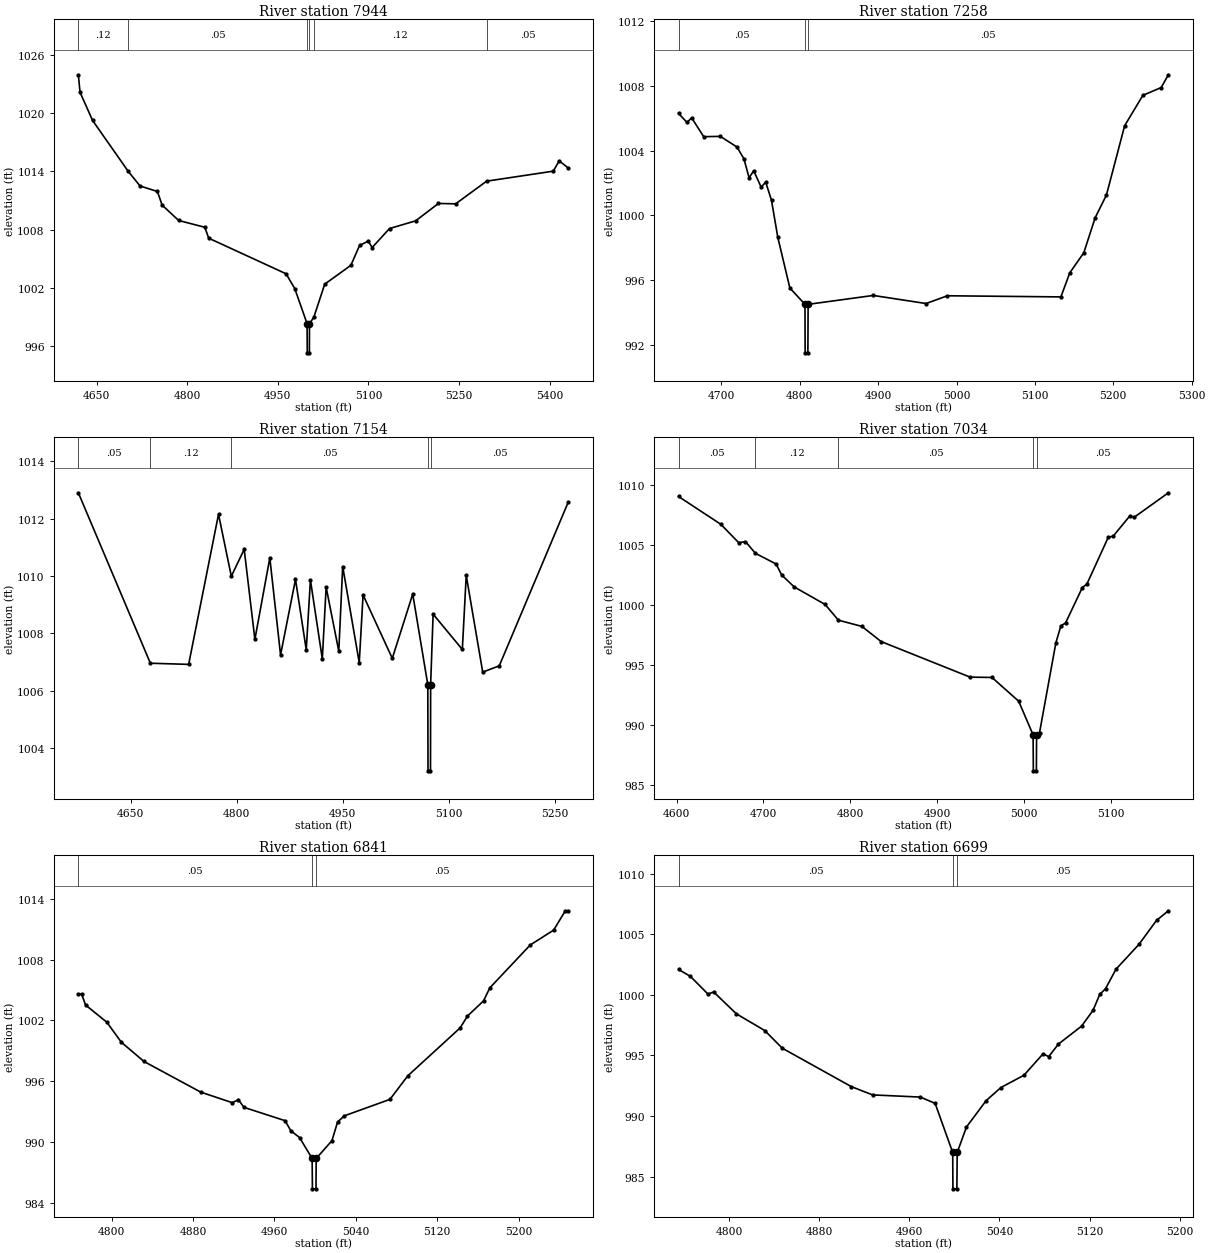
Type RM Length L Ch R = 1 ,7944    ,686,686,686
BEGIN DESCRIPTION:
SANDY 30 14.0
END DESCRIPTION:
XS GIS Cut Line= 3
      2858004.12     10170578.84      2857599.59     10170256.32
      2857342.65     10170114.18
#Sta/Elev= 30
  4619.8 1023.92  4622.6 1022.12  4643.4 1019.22  4702.4 1013.99  4721.9 1012.49
  4750.7 1011.92  4758.5 1010.52  4785.9 1008.94  4829.2 1008.24  4835.6 1007.12
  4963.7 1003.46  4978.1 1001.94  4998.5  998.33  4998.8  995.33  5002.3  995.33
  5002.5  998.33  5009.6  998.98  5027.7 1002.39    5071 1004.33  5085.4 1006.37
  5099.8 1006.82  5106.2 1006.16    5135 1008.11  5178.2  1008.9    5216 1010.69
  5244.5 1010.65  5295.7 1012.98  5406.1 1014.01  5415.9 1015.07  5430.8 1014.34
#Mann= 6 ,-1 , 0
  4619.8     .12       0  4702.4     .05       0  4998.5     .05       0
  5002.5     .05       0  5009.6     .12       0  5295.7     .05       0
Bank Sta=4998.5,5002.5
XS Rating Curve= 0 ,0
Exp/Cntr=0.3,0.1

Type RM Length L Ch R = 1 ,7258    ,104,104,104
BEGIN DESCRIPTION:
Mapping XS 66e98338
END DESCRIPTION:
XS GIS Cut Line= 3
       2858266.6      10170015.8      2857930.34     10169808.03
      2857720.27     10169715.28
#Sta/Elev= 30
  4645.4  1006.3  4656.2 1005.74  4662.1 1006.03  4677.5 1004.86  4698.7 1004.88
    4720 1004.22  4728.8 1003.49  4735.4 1002.32  4741.3 1002.75  4750.8 1001.74
  4756.6 1002.05    4764 1000.92    4772  998.64  4787.4   995.5  4806.7  994.49
  4806.9  991.49  4810.4  991.49  4810.7  994.49  4893.8  995.04  4961.2  994.54
  4988.3  995.02  5133.2  994.95  5144.5  996.44  5162.4  997.68  5176.9  999.85
  5191.2 1001.24  5214.5 1005.54  5237.8 1007.42  5261.1  1007.9  5270.3 1008.69
#Mann= 3 ,-1 , 0
  4645.4     .05       0  4806.7     .03       0  4810.7     .05       0
Bank Sta=4806.7,4810.7
XS Rating Curve= 0 ,0
Exp/Cntr=0.3,0.1

Type RM Length L Ch R = 1 ,7154    ,120,120,120
BEGIN DESCRIPTION:
SANDY 30 13.0
END DESCRIPTION:
XS GIS Cut Line= 3
      2858348.56     10169944.71      2858069.75      10169764.3
       2857739.8     10169619.78
#Sta/Elev= 30
  4576.2  1012.9    4678 1006.96  4732.1 1006.92  4774.3 1012.15  4792.4 1009.99
  4810.6 1010.93  4825.7 1007.79  4846.8 1010.63    4862 1007.25  4883.1 1009.88
  4898.3 1007.43  4904.2 1009.86    4921 1007.11  4926.4 1009.61  4944.3 1007.38
  4949.8 1010.33  4973.2 1006.98  4978.6 1009.34  5019.9 1007.13  5048.8 1009.37
  5070.1 1006.21  5070.4 1003.21  5073.9 1003.21  5074.1 1006.21  5077.6 1008.67
  5118.9 1007.44  5124.4 1010.02  5147.7 1006.65  5171.1 1006.87  5268.5 1012.57
#Mann= 5 ,-1 , 0
  4576.2     .05       0    4678     .12       0  4792.4     .05       0
  5070.1     .03       0  5074.1     .05       0
Bank Sta=5070.1,5074.1
XS Rating Curve= 0 ,0
Exp/Cntr=0.3,0.1

Type RM Length L Ch R = 1 ,7034    ,193,193,193
BEGIN DESCRIPTION:
Mapping XS 17bf66ac
END DESCRIPTION:
XS GIS Cut Line= 3
      2858334.92     10169851.79      2858077.95     10169635.83
      2857864.75     10169553.83
#Sta/Elev= 30
  4602.2 1009.08  4650.7 1006.77  4671.6 1005.22  4679.3 1005.32  4690.7 1004.34
  4714.5 1003.45    4721 1002.53  4735.3 1001.54    4771 1000.07  4786.3  998.76
  4813.4  998.24  4835.4  996.98  4937.9  994.01  4963.2  993.98  4993.9     992
  5010.5  989.19  5010.8  986.19  5014.3  986.19  5014.5  989.19  5017.9  989.37
  5036.7  996.86  5042.5  998.29  5047.9  998.53  5067.2 1001.48  5072.5 1001.78
  5097.2  1005.7  5102.5 1005.75  5121.8 1007.45  5127.2 1007.36  5166.3 1009.39
#Mann= 5 ,-1 , 0
  4602.2     .05       0  4690.7     .12       0  4786.3     .05       0
  5010.5     .05       0  5014.5     .05       0
Bank Sta=5010.5,5014.5
XS Rating Curve= 0 ,0
Exp/Cntr=0.3,0.1

Type RM Length L Ch R = 1 ,6841    ,142,142,142
BEGIN DESCRIPTION:
SANDY 30 12.0
END DESCRIPTION:
XS GIS Cut Line= 3
      2858305.66     10169603.09      2858216.02     10169495.48
      2857905.67     10169353.11
#Sta/Elev= 30
  4767.3 1004.59  4770.5 1004.59  4774.4 1003.51  4795.3 1001.81  4809.6  999.83
  4831.7  997.94  4887.7   994.9  4918.7  993.86  4924.6  994.16  4930.1   993.4
  4970.6  992.08  4976.1  991.09  4984.7  990.42  4997.1  988.35  4997.4  985.35
  5000.9  985.35  5001.1  988.35  5016.6  990.11  5022.1  991.95  5028.7  992.56
  5073.6  994.19  5091.1  996.51  5142.6 1001.25  5149.8 1002.42  5165.6 1003.92
  5171.8 1005.21  5211.5 1009.44  5234.5 1010.91    5246 1012.82  5248.8 1012.82
#Mann= 3 ,-1 , 0
  4767.3     .05       0  4997.1     .05       0  5001.1     .05       0
Bank Sta=4997.1,5001.1
XS Rating Curve= 0 ,0
Exp/Cntr=0.3,0.1

Type RM Length L Ch R = 1 ,6699    ,200,200,200
BEGIN DESCRIPTION:
Mapping XS e640296c
END DESCRIPTION:
XS GIS Cut Line= 2
      2858405.94     10169373.41      2857980.11     10169286.06
#Sta/Elev= 30
  4755.3 1002.09  4765.8 1001.52  4781.4 1000.06  4786.5 1000.23  4806.6  998.43
  4831.8  997.05  4847.4  995.59  4908.7  992.42  4927.5  991.74  4969.9  991.56
    4983  991.04  4998.6  986.99  4998.8  983.99  5002.3  983.99  5002.6  986.99
  5010.8  989.09  5028.3  991.27  5041.4  992.35  5061.8  993.36  5078.7  995.12
  5083.8   994.9  5092.4  995.93  5112.9  997.41  5123.1  998.71  5129.1 1000.03
  5134.2  1000.5  5143.5 1002.11  5163.9 1004.16  5179.5 1006.14    5190 1006.93
#Mann= 3 ,-1 , 0
  4755.3     .05       0  4998.6     .03       0  5002.6     .05       0
Bank Sta=4998.6,5002.6
XS Rating Curve= 0 ,0
Exp/Cntr=0.3,0.1

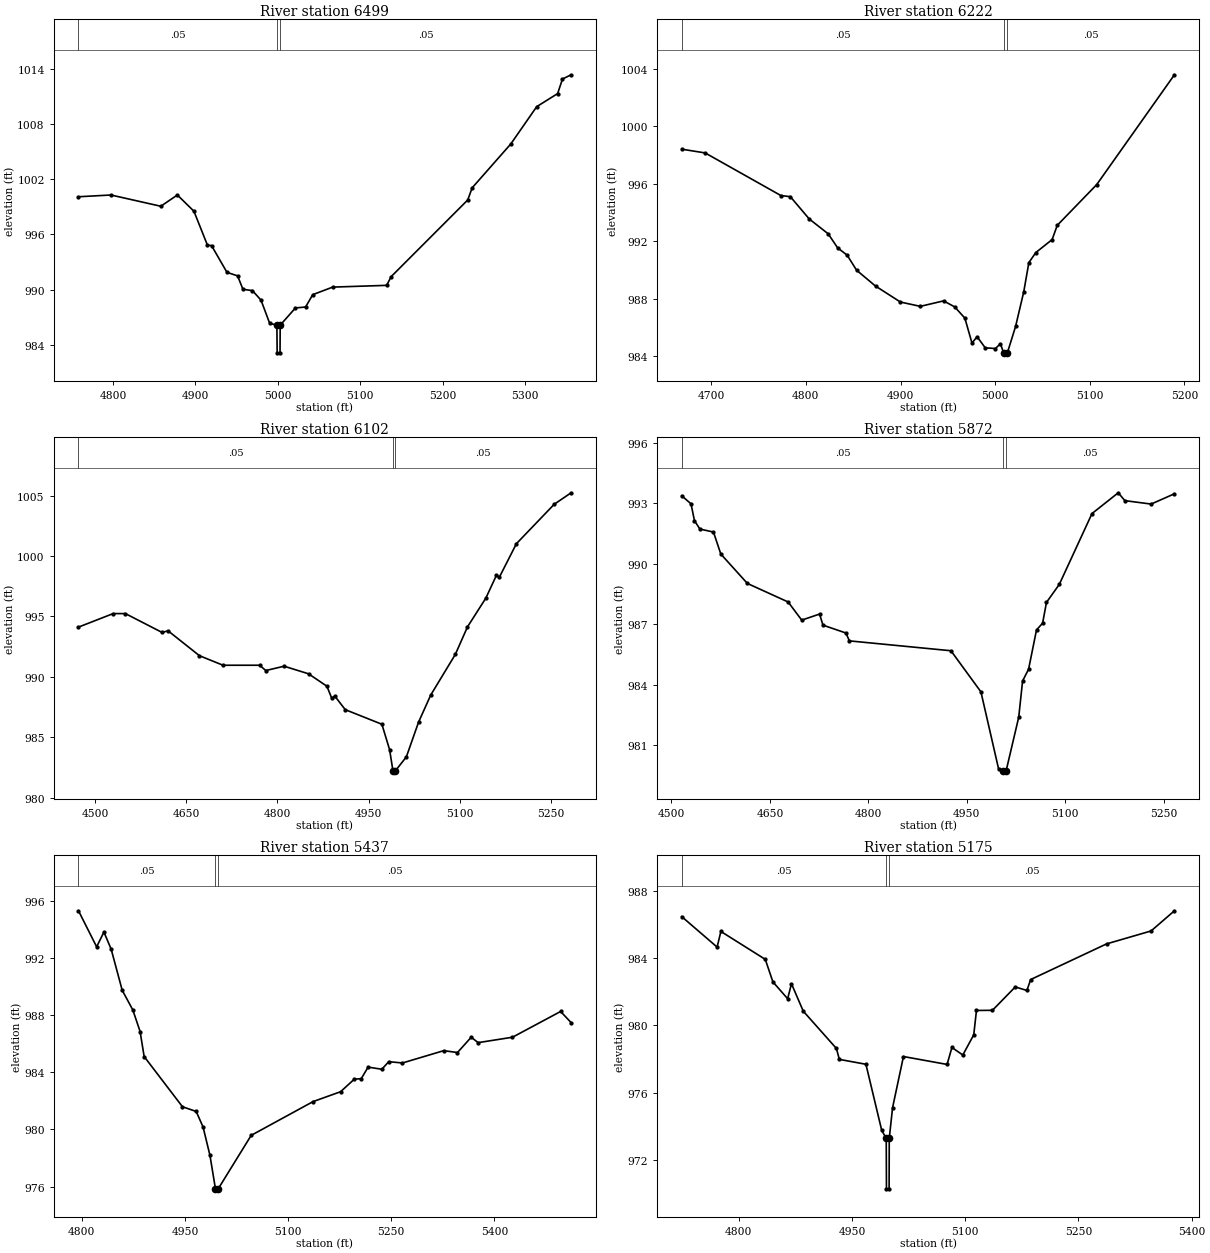
Type RM Length L Ch R = 1 ,6499    ,277,277,277
BEGIN DESCRIPTION:
SANDY 30 11.0
END DESCRIPTION:
XS GIS Cut Line= 3
      2858485.22       10169152.      2858292.89     10169135.01
      2857905.68     10169253.11
#Sta/Elev= 30
  4758.1 1000.09  4797.5 1000.28    4858  999.06  4878.1 1000.28  4898.2  998.52
  4914.6  994.84  4919.6  994.79  4938.3  991.89  4951.2  991.51  4957.7  990.05
  4969.2  989.91  4979.6  988.88  4990.1  986.37  4998.9  986.16  4999.2  983.16
  5002.7  983.16  5002.9  986.16  5021.4  988.03  5033.7  988.13  5042.4  989.47
  5066.6  990.29  5132.2  990.48  5137.4  991.41  5230.5  999.74  5235.9 1001.06
  5282.8 1005.82  5314.2 1009.86  5339.6 1011.28  5345.5 1012.86    5356 1013.32
#Mann= 3 ,-1 , 0
  4758.1     .05       0  4998.9     .05       0  5002.9     .05       0
Bank Sta=4998.9,5002.9
XS Rating Curve= 0 ,0
Exp/Cntr=0.3,0.1

Type RM Length L Ch R = 1 ,6222    ,120,120,120
BEGIN DESCRIPTION:
SANDY 30 10.0
END DESCRIPTION:
XS GIS Cut Line= 3
      2858340.33     10168985.26      2858108.02     10168990.73
      2857839.03     10169093.98
#Sta/Elev= 30
  4668.9   998.4  4693.6  998.14  4773.6  995.18  4783.6   995.1  4803.6  993.55
  4823.6  992.52  4833.6  991.54  4843.6  991.04  4853.6  989.99  4873.6  988.89
  4899.9  987.78  4920.9  987.48  4945.5  987.86  4957.3  987.44    4968  986.66
  4975.5  984.93  4980.9  985.37  4989.5   984.6  5000.2  984.55  5005.6  984.88
  5008.9  984.25  5012.9  984.25  5021.6  986.09  5030.2  988.49  5035.6  990.52
    5043  991.22  5060.2  992.12  5065.6  993.11  5107.3  995.94  5189.4 1003.57
#Mann= 3 ,-1 , 0
  4668.9     .05       0  5008.9     .03       0  5012.9     .05       0
Bank Sta=5008.9,5012.9
XS Rating Curve= 0 ,0
Exp/Cntr=0.3,0.1

Type RM Length L Ch R = 1 ,6102    ,230,230,230
BEGIN DESCRIPTION:
SANDY 30 9.0
END DESCRIPTION:
XS GIS Cut Line= 3
      2858512.58     10168905.99      2858244.69     10168881.39
      2857706.15     10168941.53
#Sta/Elev= 30
  4472.5  994.12  4529.6  995.24  4549.7  995.24    4610  993.68    4620  993.81
  4671.6  991.75  4710.4  990.96  4770.7  990.96  4780.8  990.52  4810.9  990.88
  4851.2  990.25  4881.4  989.22  4889.3  988.23  4894.3  988.41  4911.6  987.28
  4971.9  986.07  4984.6  983.96  4990.1  982.21  4994.1  982.21  5012.2  983.37
  5032.3  986.25  5052.4   988.5  5092.7  991.85  5112.8  994.14    5143  996.52
  5160.3   998.4  5165.3  998.26  5193.3 1001.03  5255.6  1004.3  5283.4 1005.25
#Mann= 3 ,-1 , 0
  4472.5     .05       0  4990.1     .03       0  4994.1     .05       0
Bank Sta=4990.1,4994.1
XS Rating Curve= 0 ,0
Exp/Cntr=0.3,0.1

Type RM Length L Ch R = 1 ,5872    ,435,435,435
BEGIN DESCRIPTION:
Mapping XS 48540cb2
END DESCRIPTION:
XS GIS Cut Line= 4
      2858422.35     10168862.26      2858102.55     10168777.52
      2857900.27     10168649.05      2857720.27     10168638.14
#Sta/Elev= 30
  4515.7  993.38  4529.8  992.98    4535  992.15  4543.3  991.73    4564  991.58
  4575.2  990.49  4615.7  989.03  4677.8  988.11  4698.5  987.21  4725.7  987.51
  4730.9  986.96  4765.9  986.57  4771.1  986.18  4925.9  985.69  4971.6  983.65
  4998.7   979.8    5006  979.73    5010  979.73  5029.2  982.39  5035.1  984.19
  5044.2  984.77  5056.3  986.72  5065.6  987.06  5071.5  988.09    5091  988.98
  5140.9   992.5  5180.9  993.53  5190.9  993.14    5231  992.97  5266.5  993.48
#Mann= 3 ,-1 , 0
  4515.7     .05       0    5006     .03       0    5010     .05       0
Bank Sta=5006,5010
XS Rating Curve= 0 ,0
Exp/Cntr=0.3,0.1

Type RM Length L Ch R = 1 ,5437    ,262,262,262
BEGIN DESCRIPTION:
SANDY 30 8.0
END DESCRIPTION:
XS GIS Cut Line= 3
      2858550.85     10168547.92       2858433.3     10168509.64
      2857840.43     10168512.38
#Sta/Elev= 30
  4795.2  995.29  4821.6  992.77  4832.2   993.8  4842.7  992.61  4858.8  989.73
  4874.2  988.36  4884.8  986.85  4890.7   985.1  4946.4  981.59  4966.4  981.26
  4976.4  980.17  4986.4  978.19  4994.4  975.85  4998.4  975.85  5046.4  979.59
  5136.4  981.95  5176.4  982.64  5196.4  983.52  5206.4  983.55  5216.4  984.36
  5236.4  984.21  5246.4  984.74  5266.4  984.65  5326.4  985.51  5346.4  985.38
  5366.4  986.45  5376.4  986.07  5426.4  986.45  5496.4  988.25  5511.7  987.47
#Mann= 3 ,-1 , 0
  4795.2     .05       0  4994.4     .05       0  4998.4     .05       0
Bank Sta=4994.4,4998.4
XS Rating Curve= 0 ,0
Exp/Cntr=0.3,0.1

Type RM Length L Ch R = 1 ,5175    ,274,274,274
BEGIN DESCRIPTION:
SANDY 30 7.0
END DESCRIPTION:
XS GIS Cut Line= 4
      2858405.71     10168303.11      2858201.99     10168324.34
      2858054.94     10168440.34      2857796.41     10168471.37
#Sta/Elev= 30
  4724.6  986.46  4771.4  984.65  4776.4  985.58  4835.2  983.92  4845.3  982.58
  4864.8  981.58  4869.9  982.47  4885.5  980.84  4929.4  978.62  4933.3  977.97
  4968.5  977.68  4989.4  973.75  4995.4  973.27  4995.7  970.27  4999.2  970.27
  4999.4  973.27  5003.8   975.1  5018.2  978.14    5076  977.67  5082.4  978.68
  5096.8  978.23  5111.3  979.43  5114.9  980.88  5136.1  980.89  5166.3  982.28
  5181.7  982.07  5186.7  982.72  5287.2  984.84  5346.2  985.61  5377.1  986.81
#Mann= 3 ,-1 , 0
  4724.6     .05       0  4995.4     .05       0  4999.4     .05       0
Bank Sta=4995.4,4999.4
XS Rating Curve= 0 ,0
Exp/Cntr=0.3,0.1

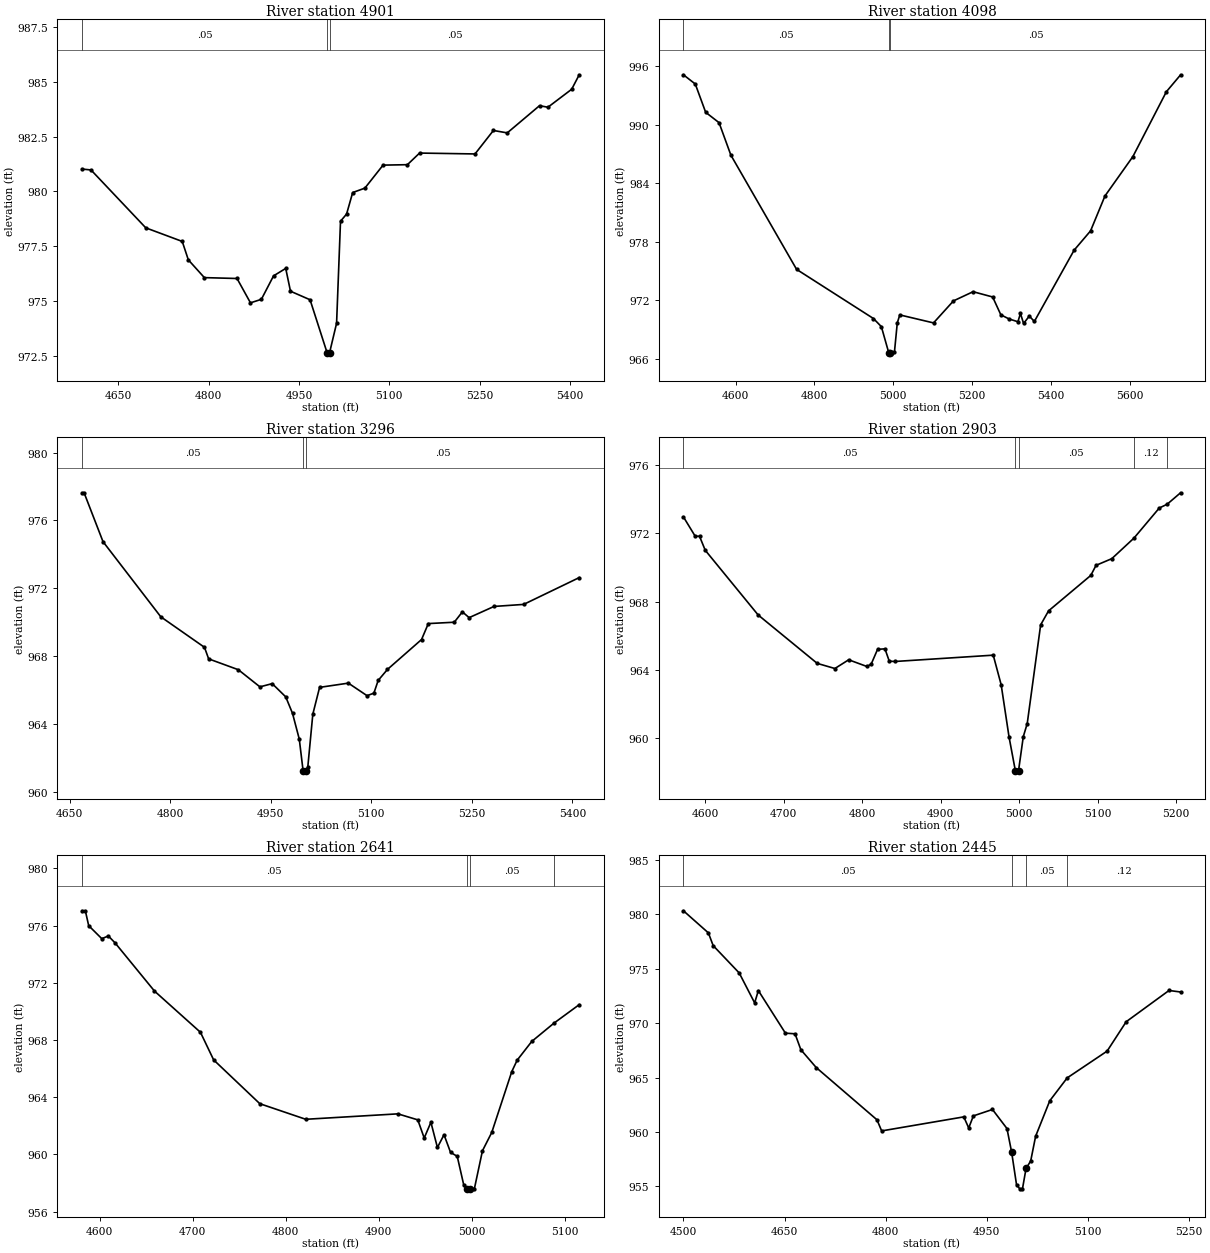
Type RM Length L Ch R = 1 ,4901    ,803,803,803
BEGIN DESCRIPTION:
Mapping XS 70dba878
END DESCRIPTION:
XS GIS Cut Line= 3
      2858340.33     10168266.36       2857714.4      10168178.9
      2857534.01     10168247.22
#Sta/Elev= 30
  4590.2  981.02    4605  980.98  4695.9  978.34  4756.4  977.72  4766.5  976.88
  4793.1  976.07  4847.3  976.03  4869.6  974.92  4887.7  975.08  4907.9  976.15
  4928.1  976.49    4936  975.45  4968.5  975.06  4996.8  972.64  5000.8  972.64
  5012.5  973.99    5019  978.64  5029.1  978.97  5039.2  979.95  5059.4  980.15
  5089.6   981.2    5130  981.22  5150.2  981.75  5242.2  981.71  5272.7  982.78
  5295.7  982.67  5349.2  983.91  5363.2  983.84  5402.6  984.66  5415.1  985.32
#Mann= 3 ,-1 , 0
  4590.2     .05       0  4996.8     .05       0  5000.8     .05       0
Bank Sta=4996.8,5000.8
XS Rating Curve= 0 ,0
Exp/Cntr=0.3,0.1

Type RM Length L Ch R = 1 ,4098    ,802,802,802
BEGIN DESCRIPTION:
SANDY 30 6.0
END DESCRIPTION:
XS GIS Cut Line= 3
      2858555.68     10168403.09       2858509.5       10167873.
      2858055.69     10167303.12
#Sta/Elev= 30
  4467.9  995.14    4498  994.19  4524.3  991.29  4558.2  990.23  4588.3  986.89
  4754.9  975.18  4949.7  970.14  4969.8  969.31  4988.6  966.62  4992.6  966.62
  5003.1  966.74  5010.2   969.7  5016.6  970.51  5102.1  969.69  5152.7  971.95
  5202.4  972.89    5252  972.35  5272.8  970.52  5293.9  970.09  5316.1  969.81
  5322.5  970.66  5330.5  969.63  5344.9  970.39  5357.8  969.84  5458.6  977.15
  5500.3  979.13  5536.8  982.71  5607.6  986.75  5692.5   993.4  5728.5  995.13
#Mann= 3 ,-1 , 0
  4467.9     .05       0  4988.6     .05       0  4992.6     .05       0
Bank Sta=4988.6,4992.6
XS Rating Curve= 0 ,0
Exp/Cntr=0.3,0.1

Type RM Length L Ch R = 1 ,3296    ,393,393,393
BEGIN DESCRIPTION:
Mapping XS ebb6bdc8
END DESCRIPTION:
XS GIS Cut Line= 3
      2858914.38     10168003.98      2858969.05     10167613.07
      2858908.92     10167271.44
#Sta/Elev= 30
  4668.6  977.63  4671.6  977.63  4699.8  974.75    4786  970.32  4851.2  968.52
  4857.4  967.84  4901.7   967.2  4933.9  966.19  4952.2  966.38  4972.4   965.6
  4982.5  964.63  4992.6  963.11  4998.3  961.24  5002.3  961.24  5005.3  961.46
  5012.8  964.58  5022.9  966.16  5065.8  966.41  5093.7  965.67  5103.9  965.82
  5110.3  966.57  5124.2  967.22    5175  968.98  5185.1  969.92  5223.8     970
  5235.9  970.61    5246  970.27  5283.1  970.93  5327.3  971.05  5410.2  972.63
#Mann= 3 ,-1 , 0
  4668.6     .05       0  4998.3     .05       0  5002.3     .05       0
Bank Sta=4998.3,5002.3
XS Rating Curve= 0 ,0
Exp/Cntr=0.3,0.1

Type RM Length L Ch R = 1 ,2903    ,262,262,262
BEGIN DESCRIPTION:
Mapping XS 154ecdd5
END DESCRIPTION:
XS GIS Cut Line= 3
      2859102.97     10167938.39      2859236.93     10167643.14
      2859274.96      10167336.2
#Sta/Elev= 30
    4572  972.95    4587  971.82  4592.5  971.82  4599.8     971  4667.2  967.22
  4742.5  964.39    4765  964.09  4782.6   964.6  4805.7  964.21  4811.2  964.34
  4819.4  965.21  4828.8  965.24  4834.3  964.52  4841.3   964.5  4966.8  964.87
  4976.9  963.14  4986.9   960.1    4995  958.11    4999  958.11  5005.1  960.11
  5010.1  960.87  5027.2  966.64  5037.3  967.46  5091.1  969.53  5097.8  970.12
  5117.9  970.51  5146.1  971.71  5178.4  973.47  5188.4  973.69  5205.5  974.36
#Mann= 5 ,-1 , 0
    4572     .05       0    4995     .05       0    4999     .05       0
  5146.1     .12       0  5188.4     .05       0
Bank Sta=4995,4999
XS Rating Curve= 0 ,0
Exp/Cntr=0.3,0.1

Type RM Length L Ch R = 1 ,2641    ,196,196,196
BEGIN DESCRIPTION:
SANDY 30 5.0
END DESCRIPTION:
XS GIS Cut Line= 3
      2859155.66     10168003.13      2859447.75       10167703.
       2859505.7     10167603.09
#Sta/Elev= 30
  4581.2  977.03  4584.7  977.03  4588.3  975.99  4602.4  975.08  4609.4  975.27
  4616.6  974.79    4659  971.42  4708.4  968.54  4722.6  966.61  4772.2  963.55
  4821.6  962.46  4920.6  962.84    4942  962.42  4948.9  961.15  4956.1  962.25
  4963.1  960.49  4970.2  961.38  4977.2  960.15  4984.4  959.87  4991.4  957.87
  4994.4   957.6  4998.4   957.6  5002.8   957.6  5011.5  960.26  5021.5  961.54
    5043  965.79  5048.8  966.59  5064.5   967.9  5088.4  969.18  5115.5  970.47
#Mann= 4 ,-1 , 0
  4581.2     .05       0  4994.4     .05       0  4998.4     .05       0
  5088.4     .12       0
Bank Sta=4994.4,4998.4
XS Rating Curve= 0 ,0
Exp/Cntr=0.3,0.1

Type RM Length L Ch R = 1 ,2445    ,134,134,134
BEGIN DESCRIPTION:
SANDY 30 4.0
END DESCRIPTION:
XS GIS Cut Line= 3
      2859155.71      10168103.1      2859455.61     10167962.95
       2859752.1      10167685.5
#Sta/Elev= 30
  4500.1  980.32  4537.1  978.29  4544.2  977.12  4582.8  974.61  4605.7  971.86
  4611.2  972.99  4651.3  969.08  4665.6  969.02  4674.2  967.56    4697  965.92
  4787.1  961.12    4794   960.1  4915.8  961.39  4923.1  960.37    4930  961.48
  4958.3  962.07  4979.8  960.32  4986.7  958.16    4994  955.16  4998.8  954.78
  5002.8  954.78  5008.1  956.65    5015  957.34  5022.3  959.61  5043.3  962.87
  5069.1  964.97  5128.3  967.43  5156.6  970.13  5220.1     973  5237.2  972.86
#Mann= 4 ,-1 , 0
  4500.1     .05       0  4986.7     .05       0  5008.1     .05       0
  5069.1     .12       0
Bank Sta=4986.7,5008.1
XS Rating Curve= 0 ,0
Exp/Cntr=0.3,0.1

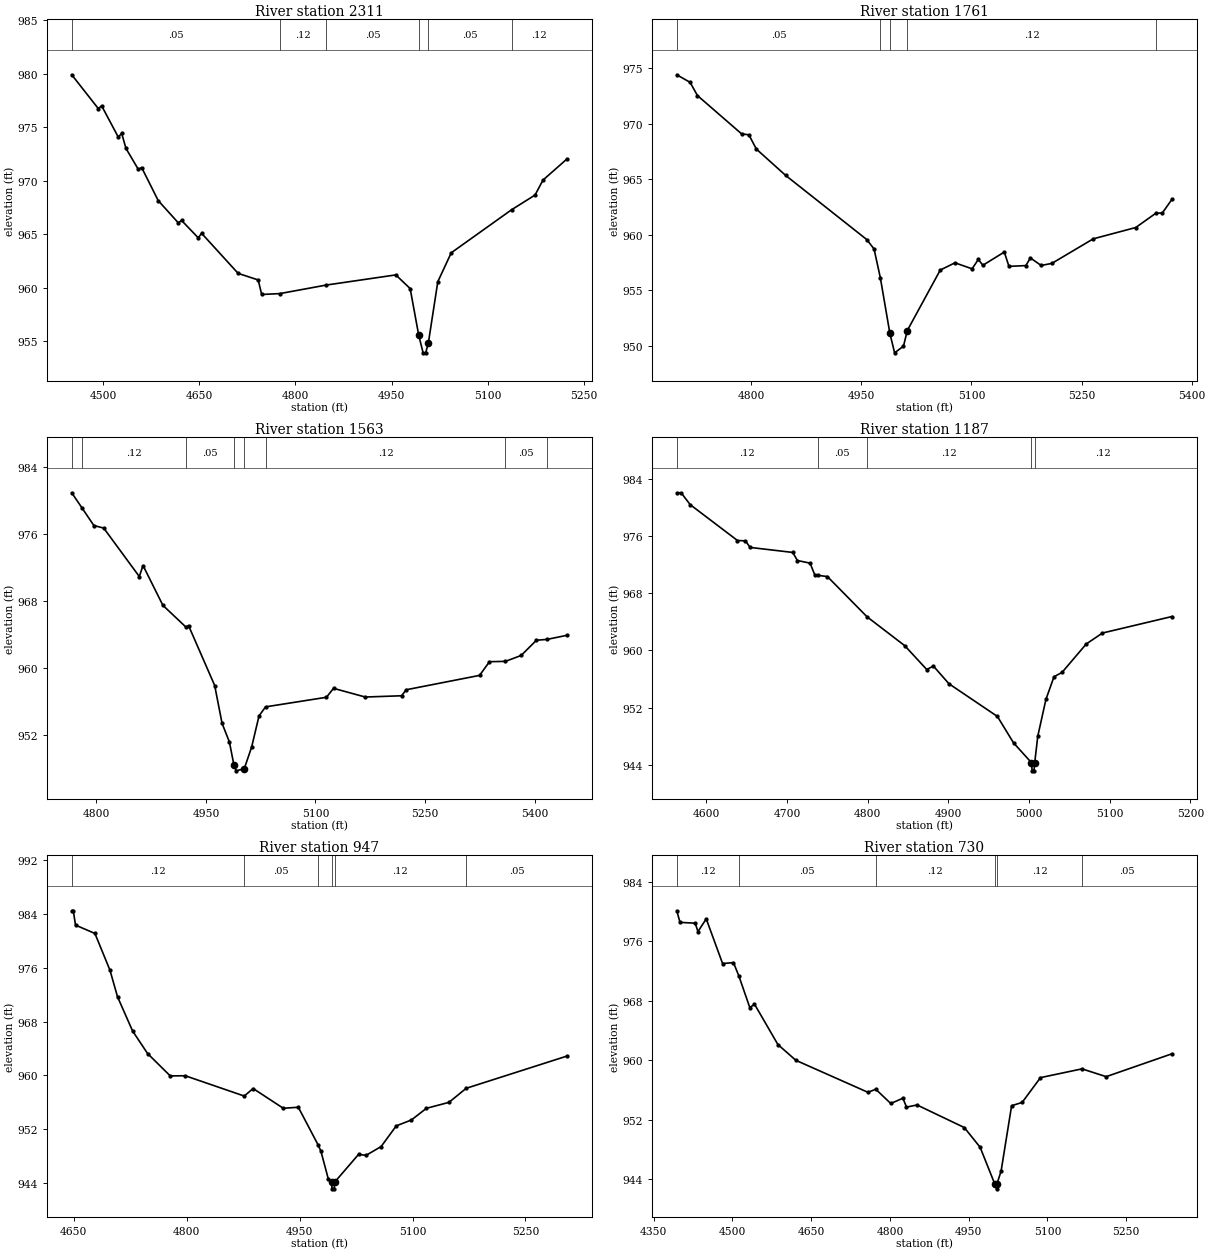
Type RM Length L Ch R = 1 ,2311    ,550,550,550
BEGIN DESCRIPTION:
SANDY 30 3.0
END DESCRIPTION:
XS GIS Cut Line= 3
       2859155.7     10168153.11      2859586.81     10168003.95
      2859846.51     10167823.54
#Sta/Elev= 30
  4451.2   979.9  4492.6  976.74  4497.9  976.99  4523.8  974.07  4529.1  974.42
  4535.8  973.01    4555  971.06  4560.3  971.22  4586.1  968.13  4617.3  966.06
  4622.6  966.27  4648.5  964.65  4653.8  965.07  4710.8  961.32    4742  960.71
  4747.5  959.35  4775.7  959.43  4848.2  960.23  4956.7  961.18  4979.1   959.9
  4992.5  955.52  4999.3  953.89  5003.3  953.89  5007.4  954.78  5022.2  960.54
  5043.2  963.25  5137.2  967.27  5173.9  968.65  5186.3  970.05  5223.6  972.02
#Mann= 6 ,-1 , 0
  4451.2     .05       0  4775.7     .12       0  4848.2     .05       0
  4992.5     .05       0  5007.4     .05       0  5137.2     .12       0
Bank Sta=4992.5,5007.4
XS Rating Curve= 0 ,0
Exp/Cntr=0.3,0.1

Type RM Length L Ch R = 1 ,1761    ,198,198,198
BEGIN DESCRIPTION:
Mapping XS 2da68bf3
END DESCRIPTION:
XS GIS Cut Line= 3
      2859127.64     10168288.24      2859515.74     10168312.83
      2859745.38     10168143.34
#Sta/Elev= 30
  4698.8   974.4  4716.9  973.72  4726.9  972.53    4787  969.08    4797  968.99
  4807.1  967.71  4847.1  965.33  4957.4  959.56  4967.4  958.71    4976  956.11
  4988.9  951.13  4995.4  949.35  5007.5  949.95  5012.7  951.36  5057.6  956.81
  5077.6  957.46  5100.9  956.92  5109.4  957.76  5115.6  957.24  5144.8  958.43
  5151.1  957.14  5174.1  957.21  5180.3   957.9    5195  957.22  5209.6  957.41
  5265.9  959.62  5323.8  960.64  5351.2  961.93    5360  961.95  5373.1  963.18
#Mann= 5 ,-1 , 0
  4698.8     .05       0    4976     .12       0  4988.9     .05       0
  5012.7     .12       0  5351.2     .05       0
Bank Sta=4988.9,5012.7
XS Rating Curve= 0 ,0
Exp/Cntr=0.3,0.1

Type RM Length L Ch R = 1 ,1563    ,376,376,376
BEGIN DESCRIPTION:
SANDY 30 2.0
END DESCRIPTION:
XS GIS Cut Line= 3
      2859485.68     10168676.37      2859540.34     10168331.97
      2859800.04     10168129.68
#Sta/Elev= 30
  4766.3  980.96  4780.3  979.15  4796.6  977.04  4810.1  976.73  4858.8  970.93
  4863.9  972.25  4891.1  967.48  4922.6  964.88  4926.2  965.06    4962  957.88
  4972.1  953.35  4982.2   951.1  4988.4  948.32  4991.5  947.66  5002.5  947.92
  5012.6  950.51  5022.7  954.24  5031.6  955.32    5115  956.47  5124.7  957.54
  5168.1   956.5  5217.9  956.65  5224.2  957.37  5324.6  959.09  5338.2  960.73
  5360.1  960.77  5381.6  961.48  5402.5   963.3  5416.9   963.4  5444.2  963.89
#Mann= 8 ,-1 , 0
  4766.3     .05       0  4780.3     .12       0  4922.6     .05       0
  4988.4     .05       0  5002.5     .05       0  5031.6     .12       0
  5360.1     .05       0  5416.9     .12       0
Bank Sta=4988.4,5002.5
XS Rating Curve= 0 ,0
Exp/Cntr=0.3,0.1

Type RM Length L Ch R = 1 ,1187    ,240,240,240
BEGIN DESCRIPTION:
Mapping XS 44c33532
END DESCRIPTION:
XS GIS Cut Line= 3
      2859685.21     10168687.33      2859843.76     10168416.71
       2859860.1      10168117.1
#Sta/Elev= 30
  4563.5  982.06  4568.9  982.06  4580.1   980.4  4638.7  975.38  4648.6  975.33
  4654.4  974.41  4707.2  973.71    4713  972.58  4728.7  972.21  4734.5  970.57
    4738  970.51  4750.2  970.33  4799.3   964.7    4846  960.66  4873.3  957.32
  4881.5  957.81  4900.8  955.33  4960.9  950.75  4980.9  947.05  5003.1  944.28
 5003.89  943.14 5006.17  943.16  5007.1  944.28  5010.9  947.99    5021  953.14
    5031  956.31    5041  956.92    5071   960.9  5091.1  962.43  5177.2  964.74
#Mann= 5 ,-1 , 0
  4563.5     .12       0    4738     .05       0  4799.3     .12       0
  5003.1     .07       0  5007.1     .12       0
Bank Sta=5003.1,5007.1
XS Rating Curve= 0 ,0
Exp/Cntr=0.3,0.1

Type RM Length L Ch R = 1 ,947     ,217,217,217
BEGIN DESCRIPTION:
Mapping XS d72f5ca5
END DESCRIPTION:
XS GIS Cut Line= 2
      2860040.56     10168763.89      2860059.66     10168106.57
#Sta/Elev= 30
  4647.4  984.51  4649.5  984.51  4652.4  982.38  4678.2  981.13  4698.2  975.65
  4708.2   971.7  4728.2  966.61  4748.2  963.24  4778.2  959.92  4798.2  959.94
  4876.5  956.92  4888.3  958.04  4928.3   955.1  4948.3  955.25  4974.7  949.62
  4978.3  948.71  4988.3   944.5  4992.6   944.1 4993.02   943.1 4995.97   943.1
  4996.6   944.1  5028.3  948.23  5038.3  948.09  5058.3   949.4  5078.4  952.48
  5098.4  953.35  5118.4  955.09  5148.4  955.98  5171.2  958.07    5305  962.87
#Mann= 6 ,-1 , 0
  4647.4     .12       0  4876.5     .05       0  4974.7     .12       0
  4992.6     .07       0  4996.6     .12       0  5171.2     .05       0
Bank Sta=4992.6,4996.6
XS Rating Curve= 0 ,0
Exp/Cntr=0.3,0.1

Type RM Length L Ch R = 1 ,730     ,0,0,0
BEGIN DESCRIPTION:
SANDY 30 1.0
END DESCRIPTION:
XS GIS Cut Line= 3
       2860149.9     10169007.14      2860248.31     10168654.52
      2860270.17     10168077.92
#Sta/Elev= 30
  4394.1  980.11  4400.2  978.55  4429.2  978.44  4434.4  977.31  4450.2  979.02
  4481.3  973.01  4502.1  973.13  4512.4  971.32  4533.2  967.07  4542.1  967.54
  4586.7   962.1  4620.9  959.98  4758.3  955.67    4773  956.09  4801.6  954.17
  4824.8  954.88  4831.6  953.68  4851.7  953.97  4941.7  950.93  4971.8  948.28
  4999.8  943.32 5003.09  942.68  5003.8  943.32  5011.8  945.08  5031.8  953.87
  5051.8  954.31  5086.8  957.65  5165.8  958.83  5211.9  957.78  5337.2  960.86
#Mann= 6 ,-1 , 0
  4394.1     .12       0  4512.4     .05       0    4773     .12       0
  4999.8     .07       0  5003.8     .12       0  5165.8     .05       0
Bank Sta=4999.8,5003.8
XS Rating Curve= 0 ,0
Exp/Cntr=0.3,0.1

Chan Stop Cuts=-1
Use User Specified Reach Order=0
Composite Channel Slope=5