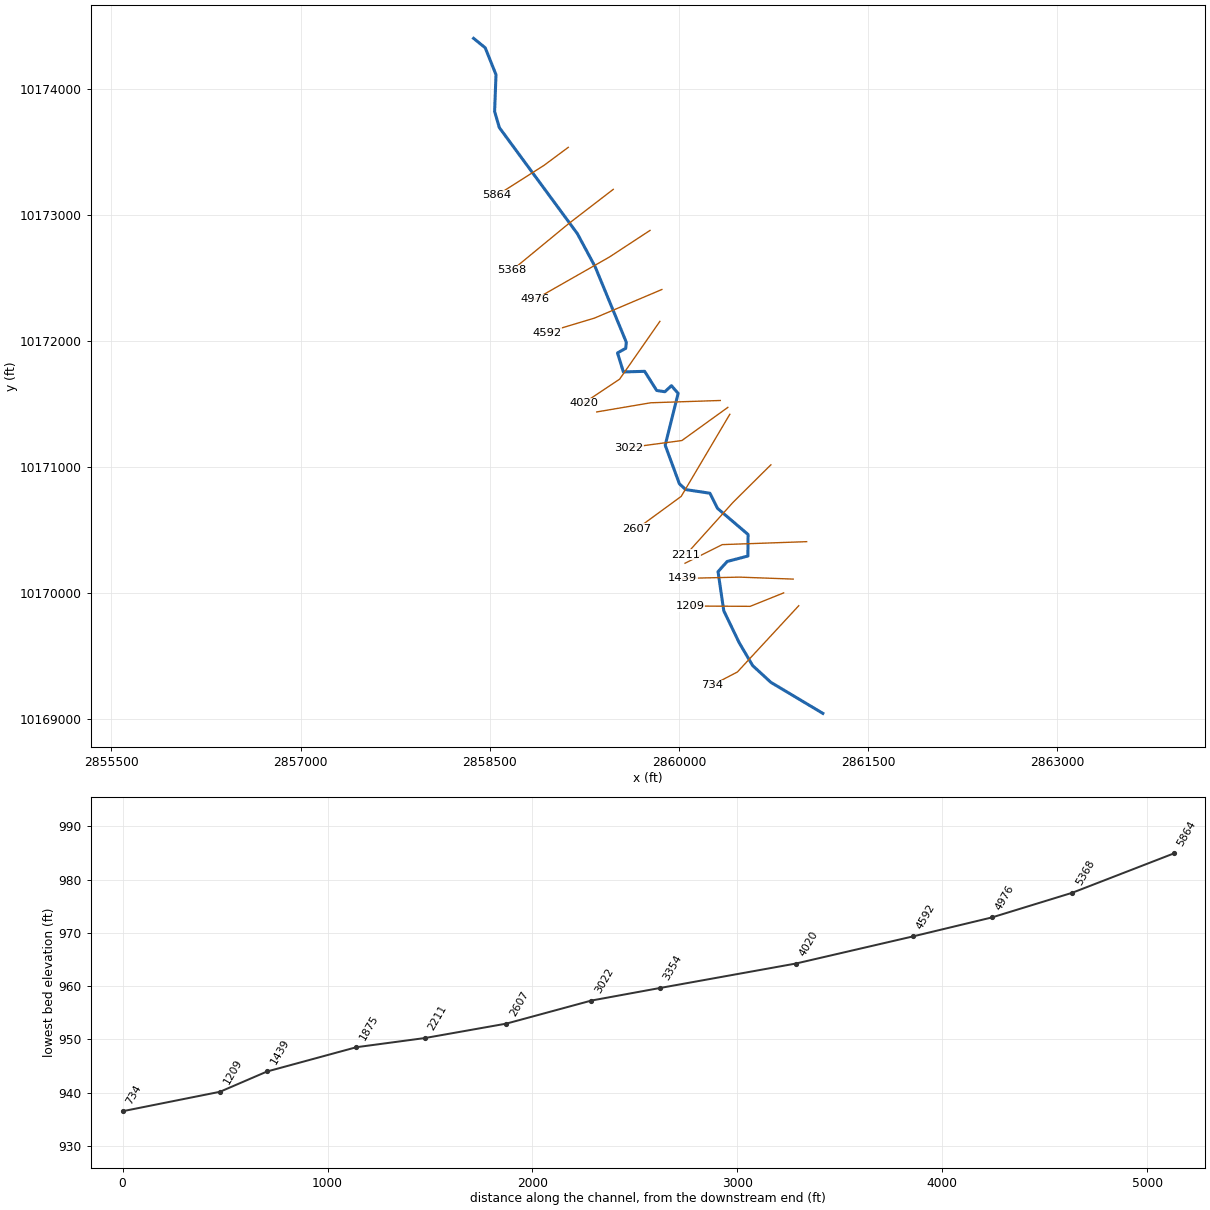
--- SANDY 31.prj (project) ---

Proj Title=SANDY 31 Base Level Engineering
Current Plan=p01
Default Exp/Contr=0.3,0.1
English Units
Geom File=g01
Flow File=f01
Plan File=p01
BEGIN DESCRIPTION:
SANDY 31
END DESCRIPTION:

--- SANDY 31.p01 (plan) ---

Plan Title=Multiple Run
Short Identifier=Multiple
Geom File=g01
Flow File=f01
Subcritical Flow
K Sum by GR= 0
Std Step Tol= 0.01
Critical Tol= 0.01
Num of Std Step Trials= 20
Max Error Tol= 0.3
Flow Tol Ratio= 0.001
Split Flow NTrial= 30
Split Flow Tol= 0.02
Split Flow Ratio= 0.02
Log Output Level= 0
Friction Slope Method= 1
Unsteady Friction Slope Method= 2
Unsteady Bridges Friction Slope Method= 1
Parabolic Critical Depth
Global Vel Dist=  1 , 1 , 1
Global Log Level= 0
CheckData=True
Encroach Param= -1, 0, 0, 0
BEGIN DESCRIPTION:
Multiple Run
END DESCRIPTION:

--- SANDY 31.f01 (steady flow) ---

Flow Title=Multiple
Number of Profiles=7
Profile Names=10-year,25-year,50-year,1pct_min,100-year,1pct_plu,500-year
River Rch & RM= SANDY 31,Reach-1,5864
      70     133     207     107     324     978     854
River Rch & RM= SANDY 31,Reach-1,3354
      78     152     240     125     378    1143    1010
Boundary for River Rch & Prof#=SANDY 31,Reach-1,1
Up Type=0
Dn Type=3
Dn Slope=0.005
Boundary for River Rch & Prof#=SANDY 31,Reach-1,2
Up Type=0
Dn Type=3
Dn Slope=0.005
Boundary for River Rch & Prof#=SANDY 31,Reach-1,3
Up Type=0
Dn Type=3
Dn Slope=0.005
Boundary for River Rch & Prof#=SANDY 31,Reach-1,4
Up Type=0
Dn Type=3
Dn Slope=0.005
Boundary for River Rch & Prof#=SANDY 31,Reach-1,5
Up Type=0
Dn Type=3
Dn Slope=0.005
Boundary for River Rch & Prof#=SANDY 31,Reach-1,6
Up Type=0
Dn Type=3
Dn Slope=0.005
Boundary for River Rch & Prof#=SANDY 31,Reach-1,7
Up Type=0
Dn Type=3
Dn Slope=0.005

--- SANDY 31.g01 (geometry) ---

Geom Title=Existing Conditions

River Reach=SANDY 31,Reach-1
Reach XY= 30
      2858372.25     10174399.00      2858464.50     10174324.00
      2858550.00     10174111.00      2858539.00     10173819.00
      2858576.50     10173691.00      2859195.25     10172850.00
      2859336.00     10172588.00      2859583.75     10171988.00
      2859578.50     10171940.00      2859513.75     10171904.00
      2859560.25     10171753.00      2859728.75     10171758.00
      2859824.50     10171606.00      2859889.25     10171596.00
      2859941.50     10171644.00      2859994.50     10171583.00
      2859892.00     10171172.00      2860004.50     10170866.00
      2860054.50     10170820.00      2860246.75     10170791.00
      2860306.75     10170671.00      2860549.25     10170464.00
      2860548.00     10170293.00      2860383.75     10170250.00
      2860311.00     10170169.00      2860356.50     10169859.00
      2860479.50     10169604.00      2860585.75     10169424.00
      2860730.25     10169291.00      2861142.50     10169045.00

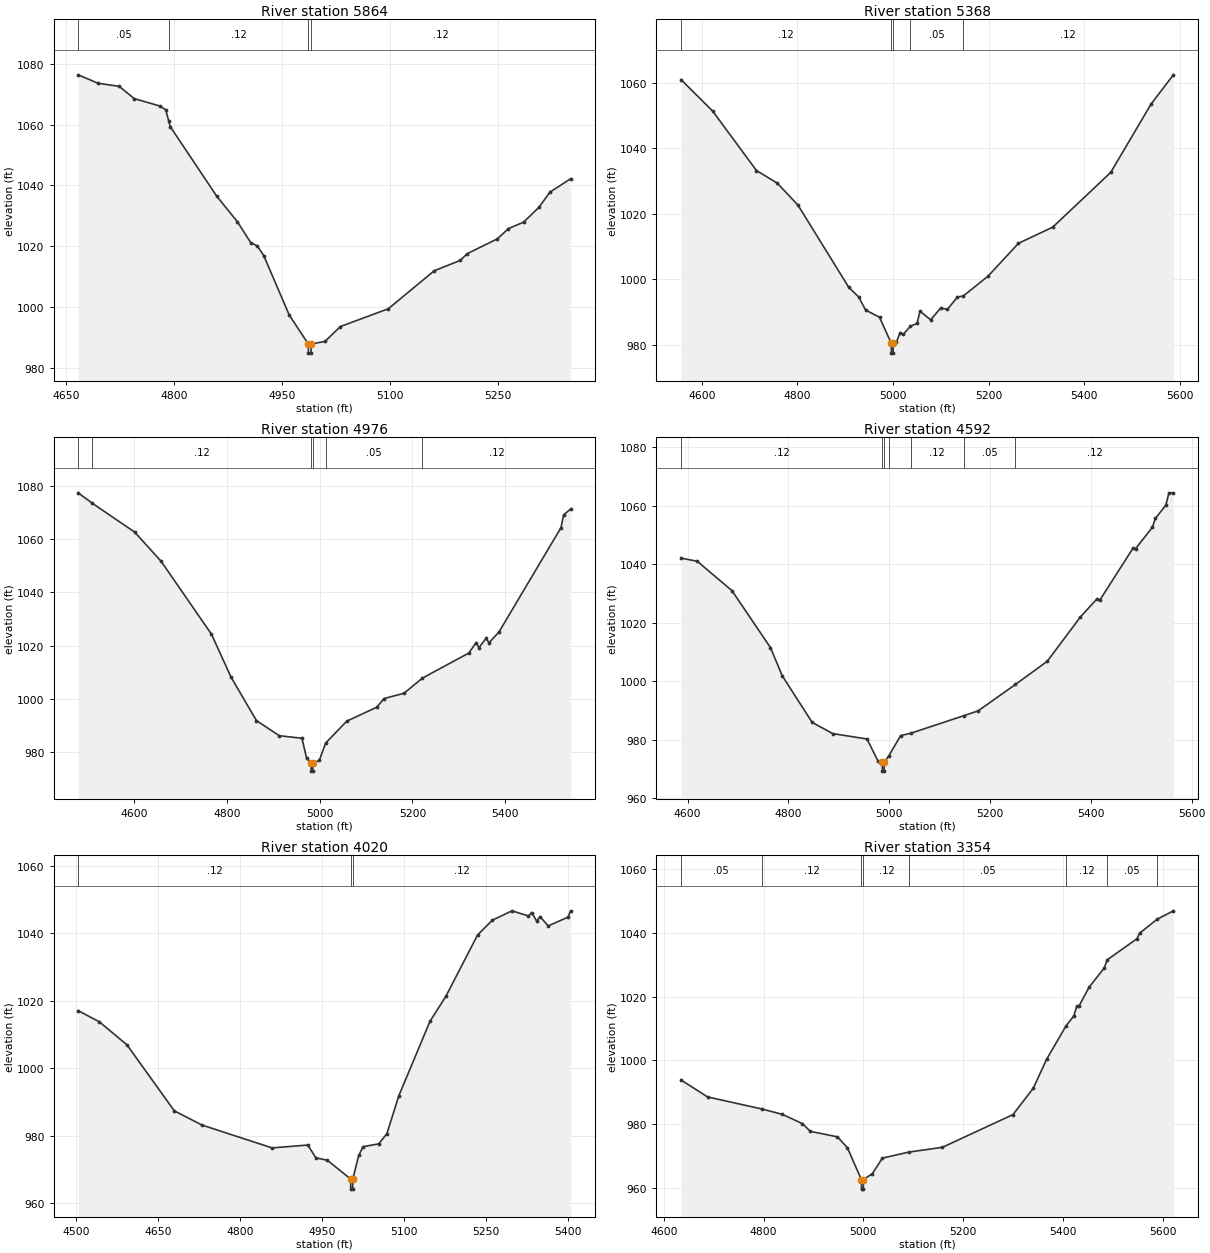
Type RM Length L Ch R = 1,5864,496,496,496
BEGIN DESCRIPTION:
SANDY 31 12.0
END DESCRIPTION:
XS GIS Cut Line= 3
      2859123.29     10173534.50      2858930.59     10173391.28
      2858555.65     10173153.09
#Sta/Elev= 30
  4666.8 1076.32  4694.6 1073.54  4723.8 1072.54  4744.7 1068.51  4780.1 1066.09
  4788.4 1064.87  4792.6 1061.21  4794.8 1059.29  4859.4 1036.43  4888.1 1028.06
  4906.8 1021.12  4915.7 1020.13  4924.6 1016.97  4960.1  997.42  4986.6  987.90
  4986.8  984.90  4990.3  984.90  4990.6  987.90  5009.7  988.74  5031.2  993.63
  5097.8  999.48  5161.5 1011.95  5197.8 1015.36  5207.1 1017.53  5249.4 1022.46
  5264.7 1025.81  5285.8 1027.94  5307.0 1032.78  5322.3 1037.77  5351.1 1042.18
#Mann=4,-1,0
  4666.8    0.05       0  4792.6    0.12       0  4986.6    0.07       0
  4990.6    0.12       0
Bank Sta=4986.6,4990.6
Exp/Cntr=0.3,0.1

Type RM Length L Ch R = 1,5368,392,392,392
BEGIN DESCRIPTION:
SANDY 31 11.0
END DESCRIPTION:
XS GIS Cut Line= 3
      2859480.08     10173201.18      2859128.50     10172931.00
      2858675.48     10172558.03
#Sta/Elev= 30
  4556.6 1061.02  4623.1 1051.37  4714.6 1033.24  4758.1 1029.41  4801.6 1022.65
  4907.6  997.61  4928.4  994.66  4942.9  990.66  4972.0  988.46  4996.6  980.51
  4996.9  977.51  5000.4  977.51  5000.6  980.51  5007.3  980.84  5015.2  983.80
  5021.7  983.22  5036.7  985.74  5050.4  986.56  5056.8  990.30  5079.0  987.68
  5099.9  991.28  5114.2  990.87  5135.0  994.64  5147.3  994.95  5198.9 1000.99
  5262.7 1011.03  5334.4 1015.97  5455.7 1032.68  5540.3 1053.59  5586.8 1062.46
#Mann=5,-1,0
  4556.6    0.12       0  4996.6    0.07       0  5000.6    0.12       0
  5036.7    0.05       0  5147.3    0.12       0
Bank Sta=4996.6,5000.6
Exp/Cntr=0.3,0.1

Type RM Length L Ch R = 1,4976,384,384,384
BEGIN DESCRIPTION:
SANDY 31 10.0
END DESCRIPTION:
XS GIS Cut Line= 3
      2859771.71     10172875.64      2859449.23     10172664.19
      2858860.53     10172328.92
#Sta/Elev= 30
  4478.4 1077.32  4509.2 1073.38  4600.4 1062.58  4657.6 1051.61  4766.2 1024.25
  4808.5 1008.12  4863.2  991.86  4912.5  986.18  4961.5  985.21  4971.6  977.66
  4981.2  975.88  4981.4  972.88  4984.9  972.88  4985.2  975.88  4999.0  976.92
  5012.6  983.41  5058.1  991.62  5122.9  996.86  5138.8 1000.12  5182.0 1002.11
  5221.5 1007.79  5321.8 1017.20  5337.6 1021.12  5343.4 1019.20  5359.2 1022.77
  5365.0 1021.02  5386.6 1025.04  5520.6 1064.23  5526.4 1069.01  5541.5 1071.29
#Mann=6,-1,0
  4478.4    0.05       0  4509.2    0.12       0  4981.2    0.07       0
  4985.2    0.12       0  5012.6    0.05       0  5221.5    0.12       0
Bank Sta=4981.2,4985.2
Exp/Cntr=0.3,0.1

Type RM Length L Ch R = 1,4592,572,572,572
BEGIN DESCRIPTION:
SANDY 31 9.0
END DESCRIPTION:
XS GIS Cut Line= 3
      2859865.50     10172406.91      2859331.64     10172180.35
      2858951.38     10172065.75
#Sta/Elev= 30
  4586.7 1042.11  4619.1 1040.99  4687.9 1030.98  4764.3 1011.53  4787.9 1001.83
  4847.2  985.96  4888.0  982.14  4955.9  980.31  4977.6  972.80  4986.1  972.33
  4986.4  969.33  4989.9  969.33  4990.1  972.33  4998.9  974.47  5022.6  981.47
  5042.5  982.25  5147.8  988.26  5176.2  989.90  5250.3  998.92  5313.4 1006.83
  5379.4 1022.01  5412.4 1028.21  5417.6 1027.67  5483.6 1045.47  5488.9 1045.34
  5521.9 1052.57  5528.0 1055.64  5548.9 1060.16  5554.8 1064.38  5563.8 1064.34
#Mann=7,-1,0
  4586.7    0.12       0  4986.1    0.05       0  4990.1    0.12       0
  4998.9    0.05       0  5042.5    0.12       0  5147.8    0.05       0
  5250.3    0.12       0
Bank Sta=4986.1,4990.1
Exp/Cntr=0.3,0.1

Type RM Length L Ch R = 1,4020,666,666,666
BEGIN DESCRIPTION:
SANDY 31 8.0
END DESCRIPTION:
XS GIS Cut Line= 3
      2859849.87     10172154.32      2859530.34     10171695.56
      2859245.72     10171505.88
#Sta/Elev= 30
  4503.1 1017.09  4541.9 1013.79  4592.6 1006.93  4679.0  987.42  4729.6  983.21
  4858.0  976.44  4923.3  977.29  4938.1  973.49  4959.1  972.78  5001.6  967.23
  5001.9  964.23  5005.4  964.23  5005.6  967.23  5016.4  974.20  5024.5  976.80
  5053.0  977.64  5068.0  980.65  5089.7  991.83  5146.8 1013.93  5175.9 1021.33
  5233.9 1039.50  5261.0 1043.89  5297.0 1046.66  5327.1 1045.14  5333.1 1046.13
  5342.1 1043.61  5348.1 1044.96  5363.2 1042.19  5399.2 1044.77  5404.2 1046.64
#Mann=3,-1,0
  4503.1    0.12       0  5001.6    0.07       0  5005.6    0.12       0
Bank Sta=5001.6,5005.6
Exp/Cntr=0.3,0.1

Type RM Length L Ch R = 1,3354,332,332,332
BEGIN DESCRIPTION:
SANDY 31 7.0
END DESCRIPTION:
XS GIS Cut Line= 3
      2860329.00     10171526.70      2859776.95     10171508.47
      2859348.92     10171435.84
#Sta/Elev= 30
  4634.5  993.89  4687.8  988.56  4796.2  984.79  4837.9  983.08  4878.0  980.16
  4893.8  977.75  4948.0  976.03  4968.0  972.61  4995.9  962.62  4996.2  959.62
  4999.8  959.62  5000.1  962.62  5018.0  964.48  5038.0  969.36  5092.1  971.27
  5158.1  972.74  5299.7  983.02  5340.3  991.30  5367.0 1000.37  5406.1 1010.90
  5421.4 1013.97  5427.3 1016.97  5432.4 1017.22  5451.9 1022.95  5482.3 1029.00
  5488.4 1031.59  5547.9 1038.20  5553.3 1039.95  5588.4 1044.33  5621.0 1046.97
#Mann=8,-1,0
  4634.5    0.05       0  4796.2    0.12       0  4995.9    0.07       0
  5000.1    0.12       0  5092.1    0.05       0  5406.1    0.12       0
  5488.4    0.05       0  5588.4    0.12       0
Bank Sta=4995.9,5000.1
Exp/Cntr=0.3,0.1

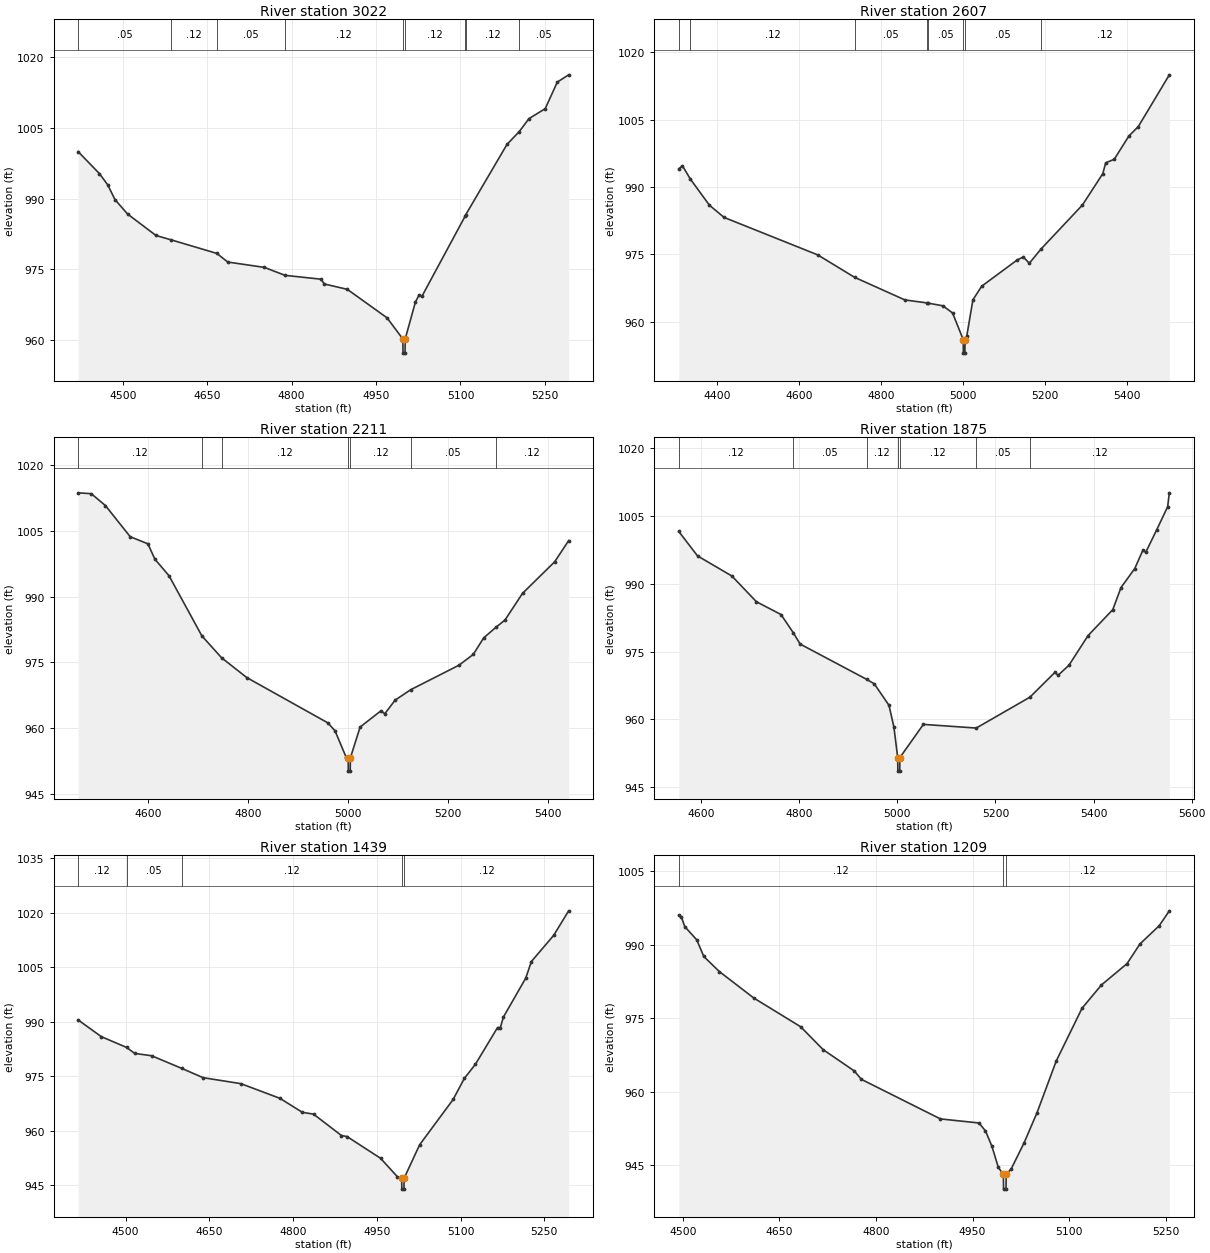
Type RM Length L Ch R = 1,3022,415,415,415
BEGIN DESCRIPTION:
SANDY 31 6.0
END DESCRIPTION:
XS GIS Cut Line= 3
      2860388.92     10171472.01      2860024.34     10171208.99
      2859605.70     10171153.11
#Sta/Elev= 30
  4420.4  999.97  4458.2  995.32  4472.9  992.96  4486.0  989.80  4508.5  986.73
  4558.8  982.20  4586.1  981.26  4667.0  978.40  4686.5  976.57  4751.5  975.44
  4788.3  973.75  4852.1  972.94  4858.2  971.92  4898.9  970.79  4969.5  964.76
  4997.6  960.28  4997.9  957.28  5001.5  957.28  5001.8  960.28  5019.9  968.08
  5026.4  969.58  5031.4  969.29  5108.4  986.30  5109.2  986.55  5182.7 1001.48
  5204.6 1004.21  5221.7 1006.94  5250.7 1009.06  5272.1 1014.68  5292.3 1016.22
#Mann=9,-1,0
  4420.4    0.05       0  4586.1    0.12       0  4667.0    0.05       0
  4788.3    0.12       0  4997.6    0.07       0  5001.8    0.12       0
  5108.4    0.05       0  5109.2    0.12       0  5204.6    0.05       0
Bank Sta=4997.6,5001.8
Exp/Cntr=0.3,0.1

Type RM Length L Ch R = 1,2607,396,396,396
BEGIN DESCRIPTION:
SANDY 31 5.0
END DESCRIPTION:
XS GIS Cut Line= 3
      2860404.54     10171417.31      2860019.14     10170766.28
      2859664.79     10170507.05
#Sta/Elev= 30
  4307.3  994.04  4316.4  994.69  4335.6  991.75  4381.9  985.94  4417.8  983.20
  4646.0  974.85  4735.8  969.85  4858.4  964.81  4913.2  964.13  4913.8  964.12
  4951.3  963.49  4974.6  961.90  5000.6  955.95  5000.9  952.95  5004.6  952.95
  5004.9  955.95  5009.4  956.86  5024.2  964.84  5045.6  967.87  5132.4  973.74
  5147.0  974.38  5161.7  972.99  5190.2  976.16  5291.2  985.98  5340.7  992.96
  5347.8  995.38  5368.6  996.16  5404.2 1001.34  5427.3 1003.46  5502.9 1014.99
#Mann=8,-1,0
  4307.3    0.05       0  4335.6    0.12       0  4735.8    0.05       0
  4913.2    0.12       0  4913.8    0.05       0  5000.6    0.05       0
  5004.9    0.05       0  5190.2    0.12       0
Bank Sta=5000.6,5004.9
Exp/Cntr=0.3,0.1

Type RM Length L Ch R = 1,2211,336,336,336
BEGIN DESCRIPTION:
SANDY 31 4.0
END DESCRIPTION:
XS GIS Cut Line= 3
      2860730.07     10171016.28      2860430.59     10170719.41
      2860055.69     10170303.12
#Sta/Elev= 30
  4459.4 1013.65  4485.9 1013.45  4514.2 1010.74  4563.8 1003.65  4599.1 1002.04
  4613.2  998.53  4641.5  994.75  4707.2  981.06  4746.6  976.08  4797.1  971.56
  4959.6  961.23  4973.8  959.41  4995.5  953.53  5000.1  953.25  5000.3  950.25
  5004.1  950.25  5004.4  953.25  5023.9  960.29  5065.7  964.00  5073.2  963.32
  5094.1  966.43  5124.9  968.78  5221.9  974.39  5250.4  976.84  5271.3  980.61
  5295.4  982.98  5313.9  984.68  5349.0  990.75  5413.3  997.94  5441.3 1002.76
#Mann=7,-1,0
  4459.4    0.12       0  4707.2    0.05       0  4746.6    0.12       0
  5000.1    0.07       0  5004.4    0.12       0  5124.9    0.05       0
  5295.4    0.12       0
Bank Sta=5000.1,5004.4
Exp/Cntr=0.3,0.1

Type RM Length L Ch R = 1,1875,436,436,436
BEGIN DESCRIPTION:
SANDY 31 3.0
END DESCRIPTION:
XS GIS Cut Line= 3
      2861013.93     10170406.91      2860344.66     10170383.47
      2860049.22     10170235.75
#Sta/Elev= 30
  4554.5 1001.60  4592.8  996.18  4662.8  991.73  4712.8  986.03  4762.9  983.20
  4787.8  979.19  4801.9  976.66  4937.2  968.86  4953.0  967.86  4983.0  963.10
  4993.0  958.31  5000.8  951.52  5001.1  948.52  5004.9  948.52  5005.2  951.52
  5053.1  958.87  5160.9  958.06  5270.3  964.90  5321.8  970.45  5327.4  969.72
  5349.8  971.96  5388.9  978.55  5439.2  984.28  5456.0  989.18  5484.0  993.38
  5500.7  997.48  5506.3  996.96  5528.7 1001.95  5551.0 1007.06  5554.5 1010.15
#Mann=7,-1,0
  4554.5    0.12       0  4787.8    0.05       0  4937.2    0.12       0
  5000.8    0.07       0  5005.2    0.12       0  5160.9    0.05       0
  5270.3    0.12       0
Bank Sta=5000.8,5005.2
Exp/Cntr=0.3,0.1

Type RM Length L Ch R = 1,1439,230,230,230
BEGIN DESCRIPTION:
SANDY 31 2.0
END DESCRIPTION:
XS GIS Cut Line= 3
      2860907.15     10170110.03      2860480.07     10170125.66
      2860028.86     10170115.29
#Sta/Elev= 30
  4415.0  990.54  4456.5  985.94  4501.9  982.96  4516.5  981.31  4546.6  980.68
  4600.9  977.18  4638.8  974.64  4706.7  972.99  4776.7  968.94  4816.7  965.10
  4836.8  964.60  4886.8  958.71  4896.8  958.43  4956.8  952.45  4986.8  947.40
  4994.6  946.96  4994.9  943.96  4998.7  943.96  4999.0  946.96  5026.8  956.17
  5086.8  968.64  5106.8  974.42  5126.8  978.35  5166.3  988.42  5171.3  988.39
  5176.8  991.31  5216.9 1002.05  5226.9 1006.60  5266.9 1013.81  5293.7 1020.56
#Mann=5,-1,0
  4415.0    0.12       0  4501.9    0.05       0  4600.9    0.12       0
  4994.6    0.07       0  4999.0    0.12       0
Bank Sta=4994.6,4999
Exp/Cntr=0.3,0.1

Type RM Length L Ch R = 1,1209,475,475,475
BEGIN DESCRIPTION:
Mapping XS d5a6cdf2
END DESCRIPTION:
XS GIS Cut Line= 3
      2860831.65     10170000.67      2860566.01     10169893.89
      2860090.02     10169896.49
#Sta/Elev= 30
  4493.5  995.98  4497.4  995.72  4502.8  993.70  4521.5  990.98  4532.4  987.60
  4556.6  984.52  4610.3  979.11  4682.9  973.27  4717.9  968.59  4766.2  964.26
  4777.3  962.54  4900.1  954.47  4960.1  953.64  4970.1  952.02  4980.1  948.90
  4990.1  944.57  4997.9  943.15  4998.2  940.15  5002.0  940.15  5002.3  943.15
  5010.1  944.29  5030.1  949.59  5050.1  955.71  5080.1  966.30  5120.1  977.03
  5150.1  981.77  5190.1  986.15  5210.1  990.15  5240.1  993.88  5255.8  996.91
#Mann=3,-1,0
  4493.5    0.12       0  4997.9    0.07       0  5002.3    0.12       0
Bank Sta=4997.9,5002.3
Exp/Cntr=0.3,0.1

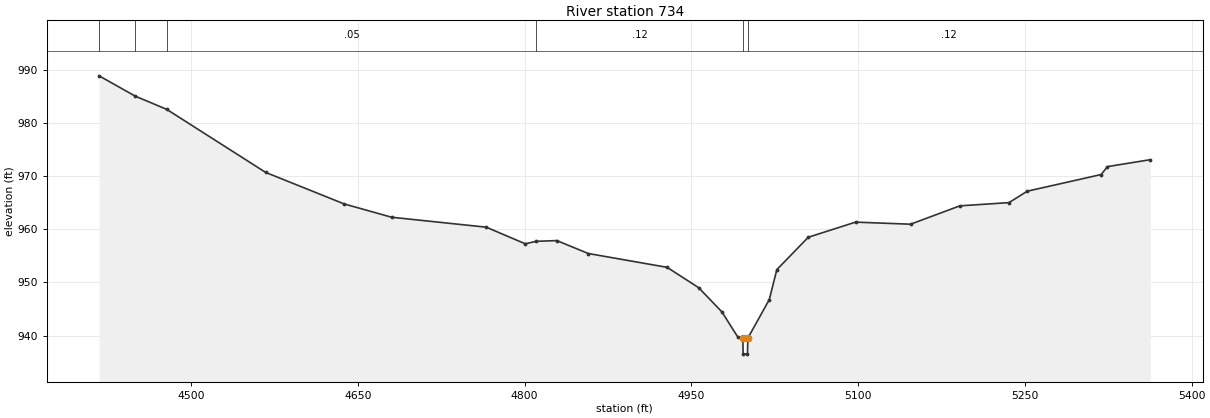
Type RM Length L Ch R = 1,734,0,0,0
BEGIN DESCRIPTION:
SANDY 31 1.0
END DESCRIPTION:
XS GIS Cut Line= 3
      2860951.42     10169899.08      2860464.45     10169373.05
      2860261.48     10169267.72
#Sta/Elev= 30
  4417.3  988.83  4449.9  985.00  4478.1  982.53  4567.1  970.67  4637.9  964.73
  4680.4  962.24  4765.5  960.37  4800.6  957.25  4810.5  957.71  4829.0  957.85
  4857.3  955.42  4928.2  952.82  4956.6  948.99  4977.5  944.44  4991.7  939.74
  4996.3  939.50  4996.6  936.50  5000.5  936.50  5000.8  939.50  5020.1  946.75
  5026.9  952.39  5055.2  958.48  5097.7  961.32  5147.2  960.93  5191.5  964.38
  5235.7  964.99  5252.2  967.14  5318.6  970.27  5324.3  971.76  5362.8  973.06
#Mann=6,-1,0
  4417.3    0.05       0  4449.9    0.12       0  4478.1    0.05       0
  4810.5    0.12       0  4996.3    0.07       0  5000.8    0.12       0
Bank Sta=4996.3,5000.8
Exp/Cntr=0.3,0.1

Chan Stop Cuts=-1