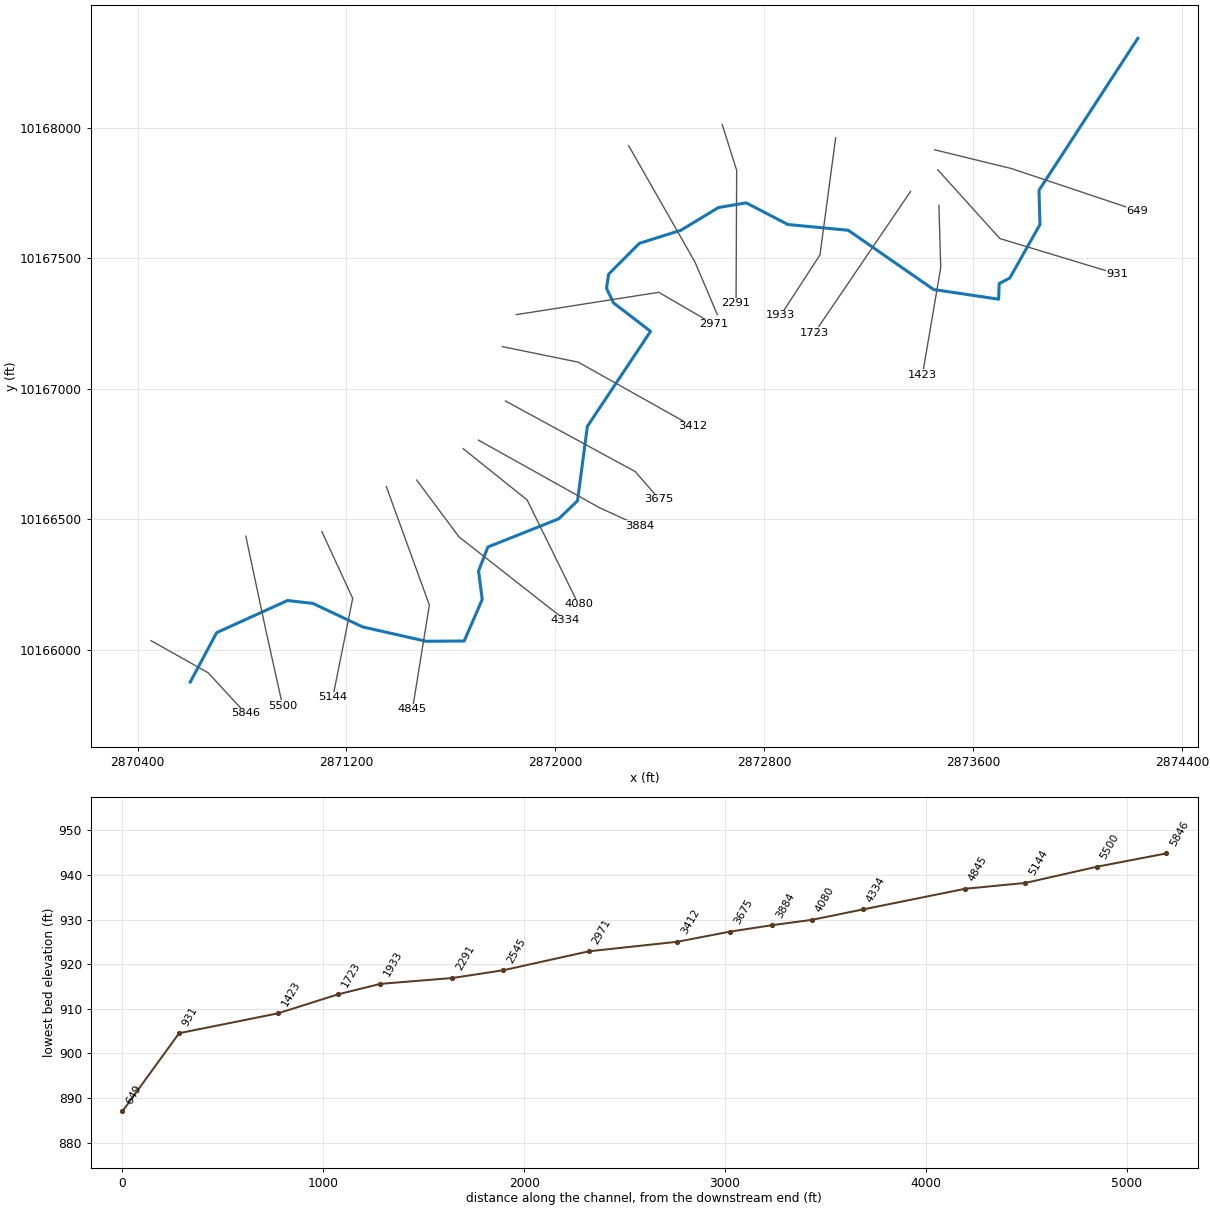
--- SANDY 34.prj (project) ---

Proj Title=SANDY 34 Base Level Engineering
Current Plan=p01
Default Exp/Contr=0.3,0.1
English Units
Geom File=g01
Flow File=f01
Plan File=p01
BEGIN DESCRIPTION:
SANDY 34
END DESCRIPTION:

--- SANDY 34.p01 (plan) ---

Plan Title=Multiple Run
Short Identifier=Multiple
Geom File=g01
Flow File=f01
Subcritical Flow
K Sum by GR= 0
Std Step Tol= 0.01
Critical Tol= 0.01
Num of Std Step Trials= 20
Max Error Tol= 0.3
Flow Tol Ratio= 0.001
Split Flow NTrial= 30
Split Flow Tol= 0.02
Split Flow Ratio= 0.02
Log Output Level= 0
Friction Slope Method= 1
Unsteady Friction Slope Method= 2
Unsteady Bridges Friction Slope Method= 1
Parabolic Critical Depth
Global Vel Dist=  1 , 1 , 1
Global Log Level= 0
CheckData=True
Encroach Param= -1, 0, 0, 0
BEGIN DESCRIPTION:
Multiple Run
END DESCRIPTION:

--- SANDY 34.f01 (steady flow) ---

Flow Title=Multiple
Number of Profiles=7
Profile Names=10-year,25-year,50-year,1pct_min,100-year,1pct_plu,500-year
River Rch & RM= SANDY 34,Reach-1,5846
     106     217     350     186     561    1695    1542
Boundary for River Rch & Prof#=SANDY 34,Reach-1,1
Up Type=0
Dn Type=3
Dn Slope=0.005
Boundary for River Rch & Prof#=SANDY 34,Reach-1,2
Up Type=0
Dn Type=3
Dn Slope=0.005
Boundary for River Rch & Prof#=SANDY 34,Reach-1,3
Up Type=0
Dn Type=3
Dn Slope=0.005
Boundary for River Rch & Prof#=SANDY 34,Reach-1,4
Up Type=0
Dn Type=3
Dn Slope=0.005
Boundary for River Rch & Prof#=SANDY 34,Reach-1,5
Up Type=0
Dn Type=3
Dn Slope=0.005
Boundary for River Rch & Prof#=SANDY 34,Reach-1,6
Up Type=0
Dn Type=3
Dn Slope=0.005
Boundary for River Rch & Prof#=SANDY 34,Reach-1,7
Up Type=0
Dn Type=3
Dn Slope=0.005

--- SANDY 34.g01 (geometry) ---

Geom Title=Existing Conditions

River Reach=SANDY 34,Reach-1
Reach XY= 30
      2870601.75     10165877.00      2870702.75     10166066.00
      2870974.00     10166189.00      2871071.25     10166178.00
      2871261.75     10166088.00      2871505.00     10166033.00
      2871650.75     10166034.00      2871719.75     10166193.00
      2871705.75     10166302.00      2871741.50     10166394.00
      2872013.00     10166502.00      2872084.75     10166571.00
      2872122.50     10166856.00      2872364.50     10167220.00
      2872222.50     10167329.00      2872195.75     10167385.00
      2872204.00     10167439.00      2872321.75     10167557.00
      2872480.75     10167607.00      2872624.50     10167694.00
      2872730.75     10167712.00      2872890.25     10167629.00
      2873121.50     10167607.00      2873448.50     10167380.00
      2873697.50     10167343.00      2873699.50     10167403.00
      2873740.25     10167424.00      2873855.75     10167629.00
      2873852.00     10167760.00      2874230.50     10168342.00

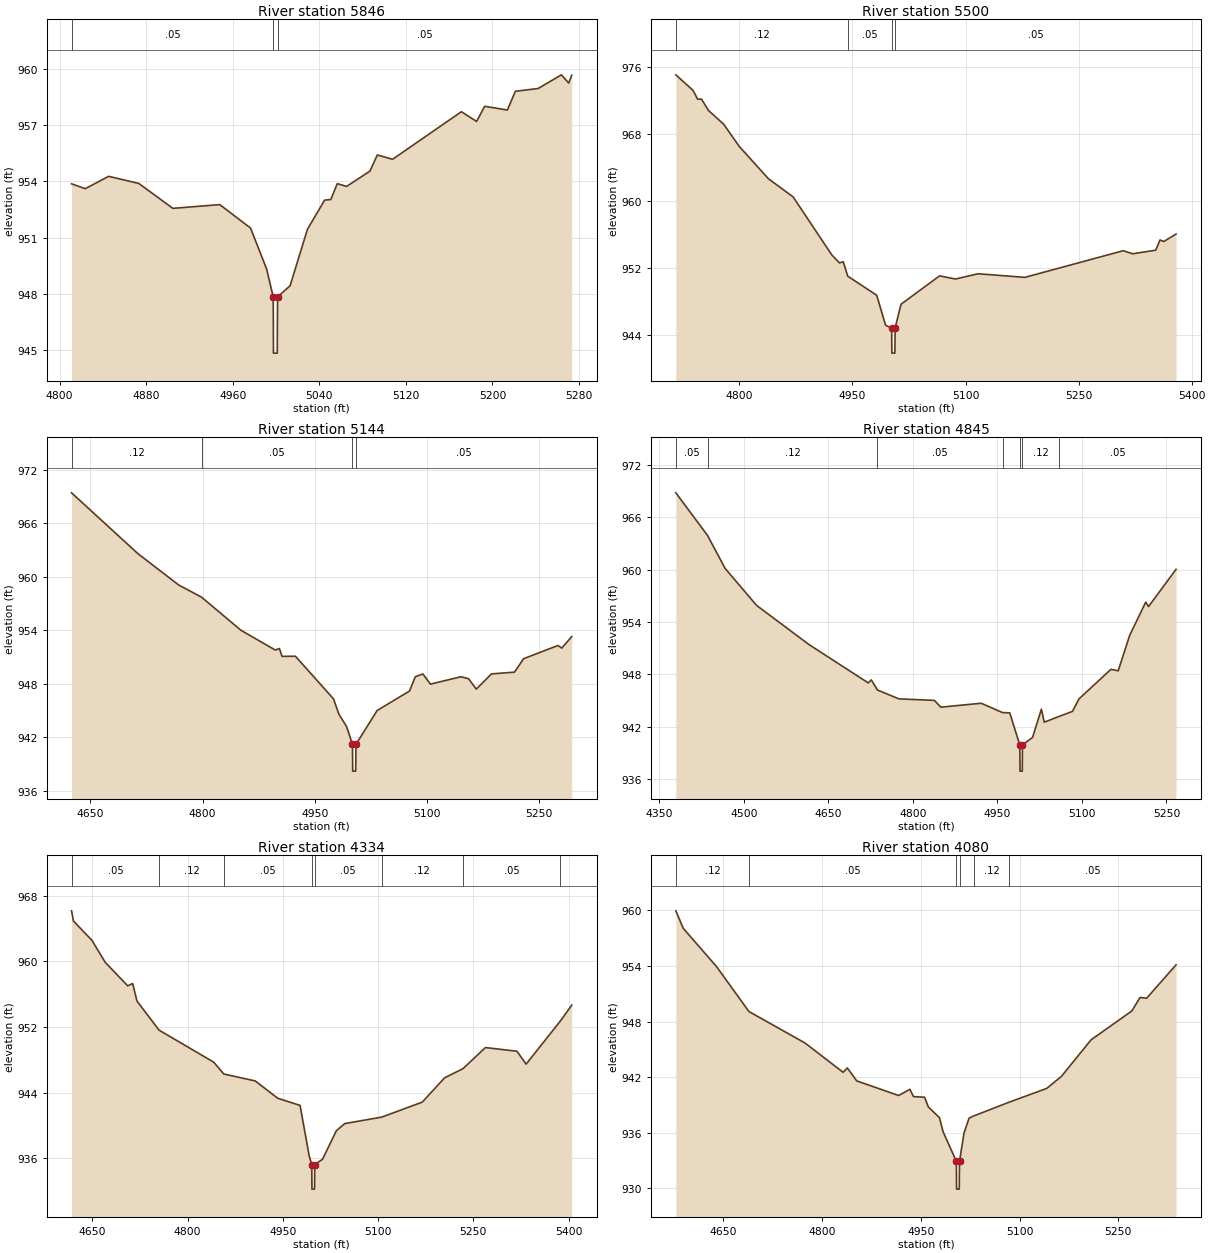
Type RM Length L Ch R = 1,5846,346,346,346
BEGIN DESCRIPTION:
SANDY 34 12.0
END DESCRIPTION:
XS GIS Cut Line= 3
      2870451.47     10166035.34      2870670.49     10165912.27
      2870813.30     10165756.85
#Sta/Elev= 30
  4811.0  953.87  4823.7  953.61  4845.3  954.27  4873.2  953.89  4904.6  952.56
  4948.0  952.76  4976.4  951.51  4991.3  949.32  4997.4  947.83  4997.6  944.83
  5001.1  944.83  5001.4  947.83  5013.0  948.43  5029.0  951.44  5044.9  953.00
  5050.6  953.03  5056.6  953.88  5065.2  953.73  5086.8  954.55  5093.6  955.41
  5107.7  955.18  5171.3  957.72  5185.4  957.20  5192.8  958.01  5213.8  957.81
  5221.2  958.81  5242.2  958.96  5263.7  959.69  5270.5  959.25  5273.3  959.67
#Mann=3,-1,0
  4811.0    0.05       0  4997.4    0.05       0  5001.4    0.05       0
Bank Sta=4997.4,5001.4
Exp/Cntr=0.3,0.1

Type RM Length L Ch R = 1,5500,356,356,356
BEGIN DESCRIPTION:
SANDY 34 11.0
END DESCRIPTION:
XS GIS Cut Line= 3
      2870814.45     10166435.35      2870890.75     10166076.97
      2870955.22     10165786.86
#Sta/Elev= 30
  4715.7  975.12  4738.4  973.27  4744.6  972.21  4749.7  972.22  4758.9  970.87
  4779.3  969.20  4799.8  966.56  4838.6  962.69  4871.3  960.52  4922.5  953.60
  4932.7  952.63  4937.8  952.76  4943.8  951.04  4982.2  948.76  4994.0  945.17
  5002.0  944.84  5002.3  941.84  5006.3  941.84  5006.6  944.84  5014.5  947.69
  5065.6  951.08  5086.6  950.70  5116.8  951.33  5178.7  950.90  5309.3  954.09
  5321.7  953.72  5352.4  954.15  5358.0  955.37  5363.1  955.19  5379.3  956.08
#Mann=4,-1,0
  4715.7    0.12       0  4943.8    0.05       0  5002.0    0.05       0
  5006.6    0.05       0
Bank Sta=5002,5006.6
Exp/Cntr=0.3,0.1

Type RM Length L Ch R = 1,5144,299,299,299
BEGIN DESCRIPTION:
SANDY 34 10.0
END DESCRIPTION:
XS GIS Cut Line= 3
      2871105.67     10166453.15      2871223.69     10166197.20
      2871147.40     10165818.06
#Sta/Elev= 30
  4624.8  969.40  4713.4  962.59  4768.0  959.07  4798.5  957.71  4851.2  954.00
  4897.1  951.78  4902.6  951.95  4906.2  951.07  4924.0  951.09  4974.9  946.31
  4982.2  944.59  4992.4  943.21  5000.3  941.21  5000.6  938.21  5004.6  938.21
  5005.0  941.21  5033.2  945.00  5076.6  947.19  5084.2  948.78  5094.4  949.10
  5104.6  947.96  5145.4  948.79  5155.6  948.56  5165.8  947.40  5186.2  949.11
  5216.8  949.30  5229.1  950.81  5274.9  952.29  5280.0  952.00  5293.4  953.29
#Mann=4,-1,0
  4624.8    0.12       0  4798.5    0.05       0  5000.3    0.05       0
  5005.0    0.05       0
Bank Sta=5000.3,5005
Exp/Cntr=0.3,0.1

Type RM Length L Ch R = 1,4845,511,511,511
BEGIN DESCRIPTION:
SANDY 34 9.0
END DESCRIPTION:
XS GIS Cut Line= 3
      2871352.62     10166625.09      2871517.33     10166171.77
      2871452.59     10165771.79
#Sta/Elev= 30
  4379.5  968.81  4435.8  963.92  4466.9  960.15  4522.7  955.91  4615.7  951.42
  4721.0  947.02  4726.3  947.37  4737.2  946.21  4775.3  945.19  4838.1  945.02
  4849.8  944.24  4921.2  944.69  4959.2  943.62  4971.9  943.59  4989.8  939.91
  4990.2  936.91  4994.2  936.91  4994.5  939.91  5012.4  940.77  5028.1  944.01
  5033.2  942.52  5059.5  943.18  5083.3  943.76  5094.8  945.19  5151.5  948.58
  5164.4  948.41  5184.6  952.45  5213.2  956.28  5218.2  955.77  5267.0  960.04
#Mann=7,-1,0
  4379.5    0.05       0  4435.8    0.12       0  4737.2    0.05       0
  4959.2    0.12       0  4989.8    0.07       0  4994.5    0.12       0
  5059.5    0.05       0
Bank Sta=4989.8,4994.5
Exp/Cntr=0.3,0.1

Type RM Length L Ch R = 1,4334,254,254,254
BEGIN DESCRIPTION:
Mapping XS ed3baffc
END DESCRIPTION:
XS GIS Cut Line= 3
      2871468.80     10166650.34      2871630.62     10166433.03
      2872037.52     10166113.99
#Sta/Elev= 30
  4617.1  966.17  4620.1  964.93  4649.3  962.57  4670.1  959.90  4705.6  957.03
  4713.4  957.31  4720.2  955.17  4755.0  951.63  4841.1  947.73  4856.9  946.29
  4906.5  945.44  4941.8  943.34  4977.1  942.46  4991.5  936.31  4995.5  935.26
  4995.8  932.26  4999.9  932.26  5000.2  935.26  5012.3  935.88  5034.3  939.38
  5047.6  940.25  5105.6  941.03  5169.6  942.86  5204.9  945.83  5233.6  946.93
  5269.1  949.51  5318.8  949.06  5333.2  947.49  5387.3  952.76  5405.1  954.68
#Mann=8,-1,0
  4617.1    0.05       0  4755.0    0.12       0  4856.9    0.05       0
  4995.5    0.05       0  5000.2    0.05       0  5105.6    0.12       0
  5233.6    0.05       0  5387.3    0.12       0
Bank Sta=4995.5,5000.2
Exp/Cntr=0.3,0.1

Type RM Length L Ch R = 1,4080,196,196,196
BEGIN DESCRIPTION:
Mapping XS 0382ffc4
END DESCRIPTION:
XS GIS Cut Line= 3
      2871646.83     10166770.58      2871891.89     10166574.07
      2872088.43     10166174.06
#Sta/Elev= 30
  4577.9  959.95  4589.2  958.06  4639.9  953.92  4688.9  949.09  4774.4  945.68
  4832.0  942.53  4838.4  943.00  4852.8  941.60  4916.4  940.03  4933.4  940.70
  4938.9  939.91  4955.8  939.84  4961.4  938.80  4978.3  937.64  4983.9  936.11
  5004.0  932.93  5004.3  929.93  5008.4  929.93  5008.8  932.93  5015.6  935.97
  5023.3  937.58  5030.3  937.82  5084.2  939.31  5141.2  940.79  5163.7  942.10
  5208.7  946.04  5270.6  949.15  5283.0  950.60  5293.0  950.52  5337.7  954.12
#Mann=6,-1,0
  4577.9    0.12       0  4688.9    0.05       0  5004.0    0.05       0
  5008.8    0.05       0  5030.3    0.12       0  5084.2    0.05       0
Bank Sta=5004,5008.8
Exp/Cntr=0.3,0.1

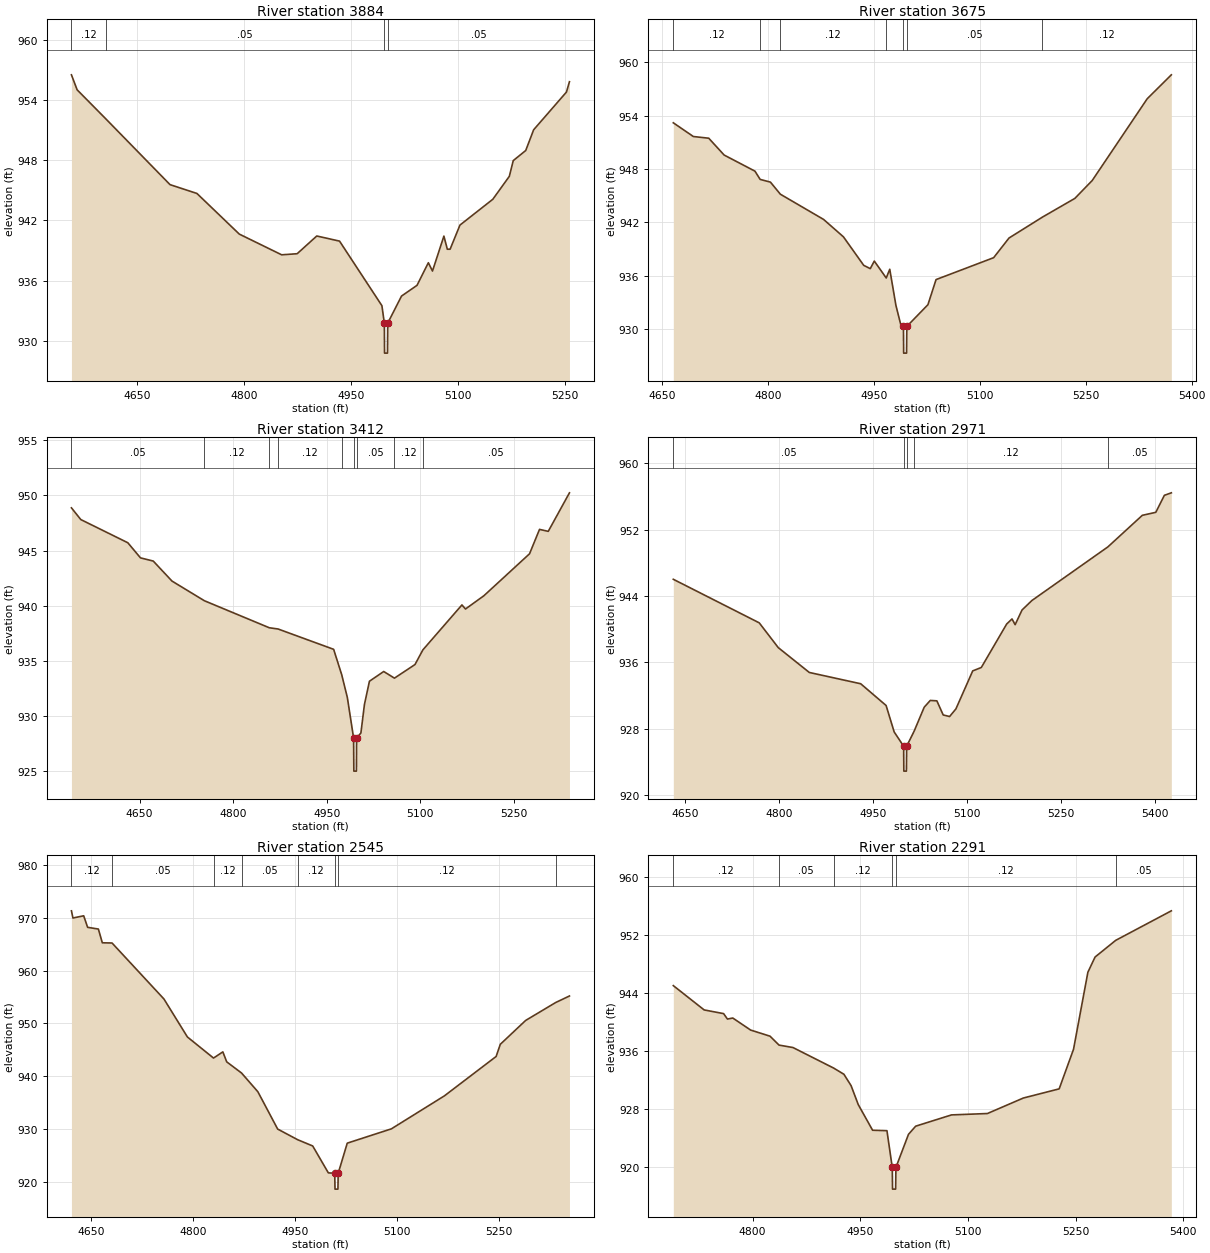
Type RM Length L Ch R = 1,3884,209,209,209
BEGIN DESCRIPTION:
SANDY 34 8.0
END DESCRIPTION:
XS GIS Cut Line= 3
      2871705.68     10166803.12      2872169.11     10166544.27
      2872321.34     10166474.93
#Sta/Elev= 30
  4557.7  956.55  4565.7  955.05  4605.5  952.18  4695.9  945.58  4733.6  944.70
  4793.0  940.64  4852.4  938.57  4874.1  938.68  4901.6  940.45  4933.5  939.94
  4992.9  933.49  4996.3  931.75  4996.6  928.75  5000.7  928.75  5001.1  931.75
  5020.4  934.45  5042.1  935.52  5058.0  937.78  5063.8  936.95  5079.8  940.44
  5084.6  939.13  5088.5  939.13  5102.3  941.54  5148.4  944.12  5171.5  946.41
  5177.0  947.98  5194.5  948.99  5205.6  951.06  5251.6  954.83  5255.8  955.86
#Mann=4,-1,0
  4557.7    0.12       0  4605.5    0.05       0  4996.3    0.05       0
  5001.1    0.05       0
Bank Sta=4996.3,5001.1
Exp/Cntr=0.3,0.1

Type RM Length L Ch R = 1,3675,263,263,263
BEGIN DESCRIPTION:
SANDY 34 7.0
END DESCRIPTION:
XS GIS Cut Line= 3
      2871808.68     10166953.24      2872305.75     10166682.74
      2872397.48     10166577.26
#Sta/Elev= 30
  4665.5  953.18  4693.9  951.64  4715.7  951.45  4737.5  949.56  4781.2  947.75
  4788.6  946.82  4803.1  946.52  4817.2  945.16  4878.4  942.33  4906.6  940.37
  4935.3  937.17  4944.6  936.80  4950.3  937.65  4967.2  935.75  4972.2  936.73
  4980.9  932.69  4988.3  930.35  4991.6  930.31  4991.9  927.31  4996.0  927.31
  4996.4  930.31  5026.3  932.75  5037.8  935.57  5119.4  938.03  5141.2  940.24
  5188.6  942.59  5234.5  944.69  5259.1  946.70  5337.0  955.88  5371.2  958.57
#Mann=7,-1,0
  4665.5    0.12       0  4788.6    0.05       0  4817.2    0.12       0
  4967.2    0.05       0  4991.6    0.05       0  4996.4    0.05       0
  5188.6    0.12       0
Bank Sta=4991.6,4996.4
Exp/Cntr=0.3,0.1

Type RM Length L Ch R = 1,3412,441,441,441
BEGIN DESCRIPTION:
SANDY 34 6.0
END DESCRIPTION:
XS GIS Cut Line= 3
      2871797.12     10167161.34      2872087.68     10167101.84
      2872525.36     10166856.17
#Sta/Elev= 30
  4540.6  948.87  4555.6  947.81  4631.0  945.71  4651.3  944.34  4671.8  944.05
  4701.8  942.24  4753.7  940.46  4857.9  938.01  4871.9  937.90  4961.0  936.06
  4974.0  933.75  4983.0  931.69  4993.0  928.03  4993.4  925.03  4997.5  925.03
  4997.8  928.03  5004.7  928.48  5010.4  931.07  5018.4  933.17  5041.3  934.05
  5058.5  933.45  5091.4  934.68  5104.1  936.01  5166.7  940.08  5172.4  939.71
  5201.9  940.91  5275.1  944.71  5291.1  946.92  5305.1  946.74  5339.1  950.23
#Mann=9,-1,0
  4540.6    0.05       0  4753.7    0.12       0  4857.9    0.05       0
  4871.9    0.12       0  4974.0    0.05       0  4993.0    0.05       0
  4997.8    0.05       0  5058.5    0.12       0  5104.1    0.05       0
Bank Sta=4993,4997.8
Exp/Cntr=0.3,0.1

Type RM Length L Ch R = 1,2971,426,426,426
BEGIN DESCRIPTION:
Mapping XS baf66a10
END DESCRIPTION:
XS GIS Cut Line= 3
      2871850.25     10167283.88      2872395.93     10167369.43
      2872605.27     10167247.51
#Sta/Elev= 30
  4631.8  946.01  4768.9  940.76  4799.3  937.77  4848.8  934.78  4930.8  933.42
  4971.3  930.80  4984.2  927.61  4999.3  925.89  4999.6  922.89  5003.7  922.89
  5004.1  925.89  5016.0  927.70  5032.1  930.59  5041.8  931.41  5052.3  931.36
  5062.4  929.66  5072.6  929.47  5082.7  930.39  5109.5  934.97  5123.2  935.38
  5163.7  940.62  5172.2  941.23  5177.2  940.54  5188.2  942.31  5203.9  943.45
  5325.1  949.91  5380.1  953.72  5401.6  954.08  5415.3  956.13  5426.4  956.43
#Mann=5,-1,0
  4631.8    0.05       0  4999.3    0.05       0  5004.1    0.05       0
  5016.0    0.12       0  5325.1    0.05       0
Bank Sta=4999.3,5004.1
Exp/Cntr=0.3,0.1

Type RM Length L Ch R = 1,2545,254,254,254
BEGIN DESCRIPTION:
SANDY 34 5.0
END DESCRIPTION:
XS GIS Cut Line= 3
      2872280.34     10167931.24      2872534.65     10167485.04
      2872620.21     10167283.87
#Sta/Elev= 30
  4620.9  971.32  4623.1  969.96  4638.9  970.38  4644.7  968.20  4660.5  967.87
  4666.3  965.27  4680.6  965.23  4756.9  954.63  4791.4  947.44  4829.8  943.45
  4843.5  944.62  4849.2  942.73  4871.0  940.62  4895.0  937.07  4924.1  930.01
  4953.4  928.00  4975.6  926.81  4998.6  921.72  5008.0  921.64  5008.4  918.64
  5012.7  918.64  5013.1  921.64  5026.4  927.34  5091.3  930.05  5169.2  936.29
  5245.3  943.75  5251.4  946.05  5288.7  950.57  5332.8  953.96  5353.1  955.20
#Mann=8,-1,0
  4620.9    0.12       0  4680.6    0.05       0  4829.8    0.12       0
  4871.0    0.05       0  4953.4    0.12       0  5008.0    0.07       0
  5013.1    0.12       0  5332.8    0.05       0
Bank Sta=5008,5013.1
Exp/Cntr=0.3,0.1

Type RM Length L Ch R = 1,2291,358,358,358
BEGIN DESCRIPTION:
Mapping XS 80ea5614
END DESCRIPTION:
XS GIS Cut Line= 3
      2872638.69     10168012.21      2872694.19     10167836.48
      2872691.88     10167326.77
#Sta/Elev= 30
  4689.4  945.03  4732.4  941.67  4759.5  941.16  4764.8  940.41  4772.3  940.55
  4797.1  938.89  4824.2  938.04  4836.7  936.81  4856.2  936.47  4912.7  933.64
  4927.1  932.78  4937.1  931.21  4947.1  928.59  4967.1  925.04  4987.1  924.98
  4994.5  919.90  4994.9  916.90  4999.2  916.90  4999.6  919.90  5017.1  924.47
  5027.1  925.60  5077.1  927.16  5127.1  927.35  5177.1  929.49  5227.1  930.76
  5247.1  936.23  5267.1  946.88  5277.1  948.98  5305.9  951.29  5383.4  955.37
#Mann=6,-1,0
  4689.4    0.12       0  4836.7    0.05       0  4912.7    0.12       0
  4994.5    0.07       0  4999.6    0.12       0  5305.9    0.05       0
Bank Sta=4994.5,4999.6
Exp/Cntr=0.3,0.1

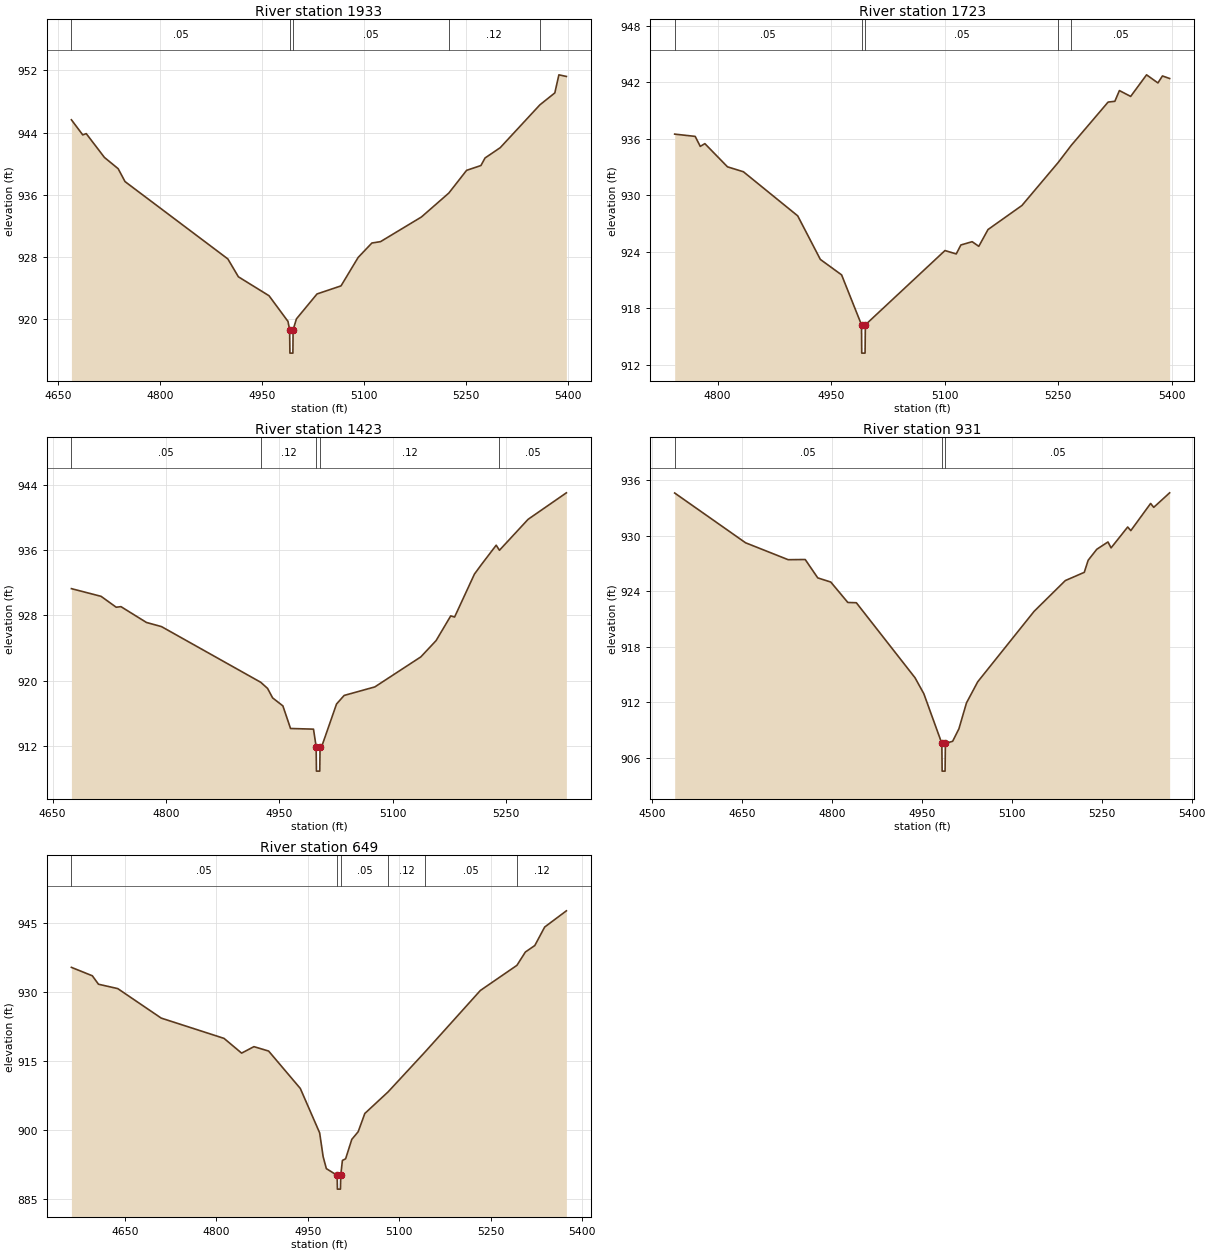
Type RM Length L Ch R = 1,1933,210,210,210
BEGIN DESCRIPTION:
SANDY 34 4.0
END DESCRIPTION:
XS GIS Cut Line= 3
      2873073.37     10167961.30      2873013.26     10167512.78
      2872862.96     10167281.56
#Sta/Elev= 30
  4669.9  945.64  4686.6  943.69  4691.7  943.86  4718.5  940.79  4738.7  939.34
  4748.8  937.68  4900.1  927.72  4915.6  925.42  4960.7  922.98  4988.6  919.67
  4991.0  918.59  4991.4  915.59  4995.8  915.59  4996.1  918.59  5001.0  920.00
  5031.3  923.21  5066.6  924.25  5091.8  927.91  5112.0  929.77  5124.8  929.95
  5184.9  933.12  5225.2  936.20  5251.4  939.13  5272.5  939.75  5278.5  940.72
  5300.9  942.05  5359.3  947.57  5381.2  949.10  5387.2  951.43  5398.2  951.22
#Mann=5,-1,0
  4669.9    0.05       0  4991.0    0.05       0  4996.1    0.05       0
  5225.2    0.12       0  5359.3    0.05       0
Bank Sta=4991,4996.1
Exp/Cntr=0.3,0.1

Type RM Length L Ch R = 1,1723,300,300,300
BEGIN DESCRIPTION:
Mapping XS 1362f69f
END DESCRIPTION:
XS GIS Cut Line= 2
      2873360.08     10167755.56      2872992.46     10167214.54
#Sta/Elev= 30
  4743.3  936.48  4770.4  936.24  4777.1  935.18  4783.2  935.47  4813.1  933.01
  4834.1  932.49  4905.9  927.81  4935.8  923.19  4963.9  921.55  4990.2  916.25
  4990.5  913.25  4994.9  913.25  4995.3  916.25  5100.5  924.13  5115.4  923.77
  5121.5  924.72  5136.4  925.07  5145.2  924.58  5157.4  926.36  5202.2  928.91
  5250.0  933.46  5267.6  935.31  5316.1  939.88  5325.0  939.96  5331.0  941.10
  5345.9  940.48  5366.9  942.77  5381.9  941.91  5387.9  942.65  5397.4  942.38
#Mann=5,-1,0
  4743.3    0.05       0  4990.2    0.05       0  4995.3    0.05       0
  5250.0    0.12       0  5267.6    0.05       0
Bank Sta=4990.2,4995.3
Exp/Cntr=0.3,0.1

Type RM Length L Ch R = 1,1423,492,492,492
BEGIN DESCRIPTION:
SANDY 34 3.0
END DESCRIPTION:
XS GIS Cut Line= 3
      2873468.74     10167702.39      2873475.68     10167464.23
      2873405.68     10167053.10
#Sta/Elev= 30
  4674.9  931.28  4714.2  930.34  4734.2  929.01  4740.5  929.08  4774.2  927.15
  4794.2  926.64  4925.5  919.84  4934.6  919.09  4941.3  917.93  4954.9  916.95
  4965.0  914.19  4995.4  914.11  4998.9  911.98  4999.3  908.98  5003.7  908.98
  5004.1  911.98  5006.6  912.07  5025.9  917.18  5036.0  918.23  5076.6  919.27
  5137.5  922.94  5157.7  924.93  5177.1  927.95  5182.2  927.81  5208.5  933.06
  5218.6  934.33  5237.3  936.59  5241.6  935.97  5279.5  939.75  5330.2  942.99
#Mann=5,-1,0
  4674.9    0.05       0  4925.5    0.12       0  4998.9    0.07       0
  5004.1    0.12       0  5241.6    0.05       0
Bank Sta=4998.9,5004.1
Exp/Cntr=0.3,0.1

Type RM Length L Ch R = 1,931,282,282,282
BEGIN DESCRIPTION:
SANDY 34 2.0
END DESCRIPTION:
XS GIS Cut Line= 3
      2873464.11     10167838.80      2873702.26     10167575.21
      2874151.89     10167439.17
#Sta/Elev= 30
  4538.3  934.64  4656.5  929.25  4727.5  927.42  4755.9  927.44  4776.8  925.45
  4798.5  925.00  4826.9  922.79  4841.1  922.76  4938.9  914.64  4953.6  912.91
  4983.6  907.53  4984.1  904.53  4989.0  904.53  4989.5  907.53  5001.6  907.76
  5012.0  909.10  5024.7  911.92  5043.4  914.20  5137.4  921.83  5189.4  925.16
  5221.0  926.05  5227.5  927.36  5241.9  928.55  5260.5  929.34  5265.7  928.70
  5293.4  930.96  5298.6  930.57  5331.6  933.51  5336.8  933.09  5363.3  934.66
#Mann=3,-1,0
  4538.3    0.05       0  4983.6    0.05       0  4989.5    0.05       0
Bank Sta=4983.6,4989.5
Exp/Cntr=0.3,0.1

Type RM Length L Ch R = 1,649,0,0,0
BEGIN DESCRIPTION:
SANDY 34 1.0
END DESCRIPTION:
XS GIS Cut Line= 3
      2873452.57     10167915.09      2873746.19     10167843.41
      2874229.46     10167681.55
#Sta/Elev= 30
  4562.3  935.29  4596.6  933.46  4606.7  931.62  4638.3  930.67  4709.6  924.25
  4812.6  919.84  4841.5  916.63  4861.7  918.04  4885.8  917.08  4937.8  908.94
  4969.5  899.28  4975.2  894.11  4980.5  891.50  4998.2  890.04  4998.6  887.04
  5003.6  887.04  5004.1  890.04  5006.8  893.28  5012.1  893.64  5022.2  897.86
  5032.7  899.53  5043.6  903.50  5081.8  908.20  5141.8  916.80  5233.1  930.26
  5293.1  935.73  5306.9  938.62  5322.4  940.04  5338.6  944.06  5374.2  947.59
#Mann=6,-1,0
  4562.3    0.05       0  4998.2    0.05       0  5004.1    0.05       0
  5081.8    0.12       0  5141.8    0.05       0  5293.1    0.12       0
Bank Sta=4998.2,5004.1
Exp/Cntr=0.3,0.1

Chan Stop Cuts=-1