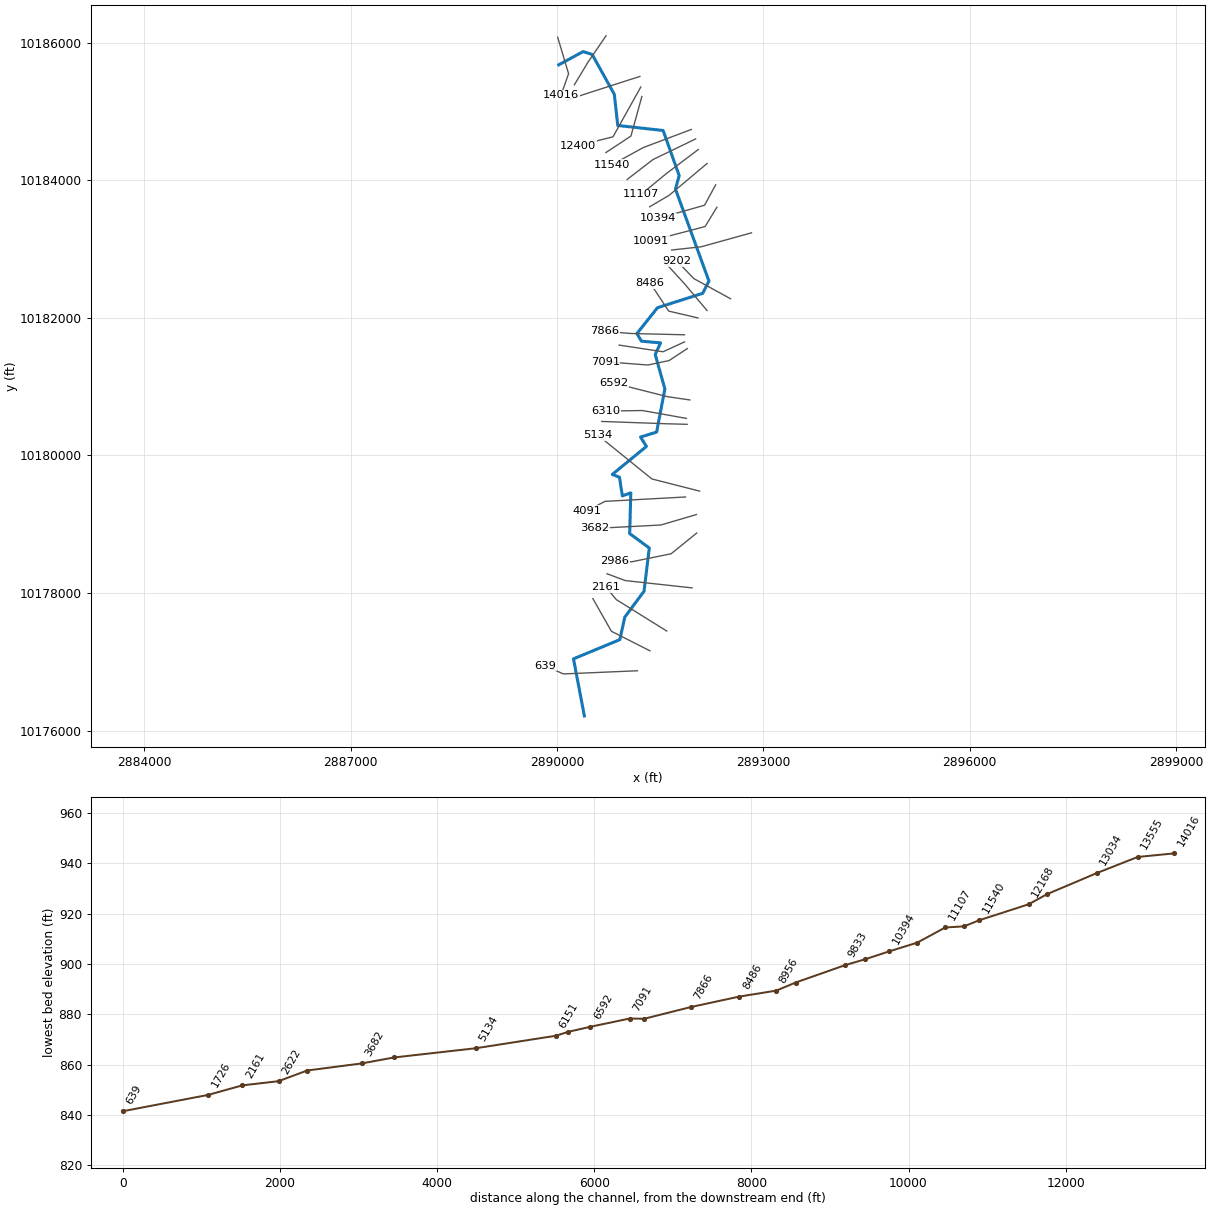
--- SANDY 37.prj (project) ---

Proj Title=SANDY 37 Base Level Engineering
Current Plan=p01
Default Exp/Contr=0.3,0.1
English Units
Geom File=g01
Flow File=f01
Plan File=p01
Y Axis Title=Elevation
X Axis Title(PF)=Main Channel Distance
X Axis Title(XS)=Station
BEGIN DESCRIPTION:
SANDY 37
END DESCRIPTION:
DSS Export Rating Curves= 0
DSS Export Rating Curve Sorted= 0
DSS Export Volume Flow Curves= 0
DXF OffsetX= 0
DXF OffsetY= 0
DXF ScaleX= 1
DXF ScaleY= 10

--- SANDY 37.p01 (plan) ---

Plan Title=Multiple Run
Short Identifier=Multiple
Geom File=g01
Flow File=f01
Subcritical Flow
K Sum by GR= 0
Std Step Tol= 0.01
Critical Tol= 0.01
Num of Std Step Trials= 20
Max Error Tol= 0.3
Flow Tol Ratio= 0.001
Split Flow NTrial= 30
Split Flow Tol= 0.02
Split Flow Ratio= 0.02
Log Output Level= 0
Friction Slope Method= 1
Unsteady Friction Slope Method= 2
Unsteady Bridges Friction Slope Method= 1
Parabolic Critical Depth
Global Vel Dist=  1 , 1 , 1
Global Log Level= 0
CheckData=True
Encroach Param= -1, 0, 0, 0
BEGIN DESCRIPTION:
Multiple Run
END DESCRIPTION:

--- SANDY 37.f01 (steady flow) ---

Flow Title=Multiple
Program Version=4.10
Number of Profiles= 7
Profile Names=10-year,25-year,50-year,1pct_min,100-year,1pct_plu,500-year
River Rch & RM=SANDY 37,Reach-1         ,14016
      67     129     201     104     315     950     829
River Rch & RM=SANDY 37,Reach-1         ,7866
      77     152     240     126     379    1145    1014
River Rch & RM=SANDY 37,Reach-1         ,5134
      92     186     296     157     473    1428    1284
River Rch & RM=SANDY 37,Reach-1         ,2986
      92     186     296     157     473    1428    1284
Boundary for River Rch & Prof#=SANDY 37,Reach-1         , 1
Up Type= 0
Dn Type= 3
Dn Slope=0.005
Boundary for River Rch & Prof#=SANDY 37,Reach-1         , 2
Up Type= 0
Dn Type= 3
Dn Slope=0.005
Boundary for River Rch & Prof#=SANDY 37,Reach-1         , 3
Up Type= 0
Dn Type= 3
Dn Slope=0.005
Boundary for River Rch & Prof#=SANDY 37,Reach-1         , 4
Up Type= 0
Dn Type= 3
Dn Slope=0.005
Boundary for River Rch & Prof#=SANDY 37,Reach-1         , 5
Up Type= 0
Dn Type= 3
Dn Slope=0.005
Boundary for River Rch & Prof#=SANDY 37,Reach-1         , 6
Up Type= 0
Dn Type= 3
Dn Slope=0.005
Boundary for River Rch & Prof#=SANDY 37,Reach-1         , 7
Up Type= 0
Dn Type= 3
Dn Slope=0.005
DSS Import GetInterval= 0
DSS Import GetPeak= 0
DSS Import FillOption= 0

--- SANDY 37.g01 (geometry) ---

Geom Title=Existing Conditions

River Reach=SANDY 37,Reach-1
Reach XY= 30
      2890027.75     10185678.00      2890382.50     10185870.00
      2890513.25     10185828.00      2890835.25     10185249.00
      2890885.00     10184796.00      2891544.50     10184723.00
      2891778.25     10184067.00      2891724.25     10183871.00
      2892211.00     10182533.00      2892120.00     10182356.00
      2891463.50     10182147.00      2891163.75     10181771.00
      2891229.75     10181660.00      2891507.50     10181635.00
      2891430.00     10181466.00      2891570.25     10180966.00
      2891450.25     10180339.00      2891216.00     10180266.00
      2891302.25     10180130.00      2890805.75     10179723.00
      2890909.75     10179683.00      2890952.00     10179411.00
      2891075.00     10179455.00      2891058.50     10178863.00
      2891343.50     10178654.00      2891267.25     10178025.00
      2890987.75     10177649.00      2890915.50     10177321.00
      2890241.75     10177042.00      2890399.75     10176212.00

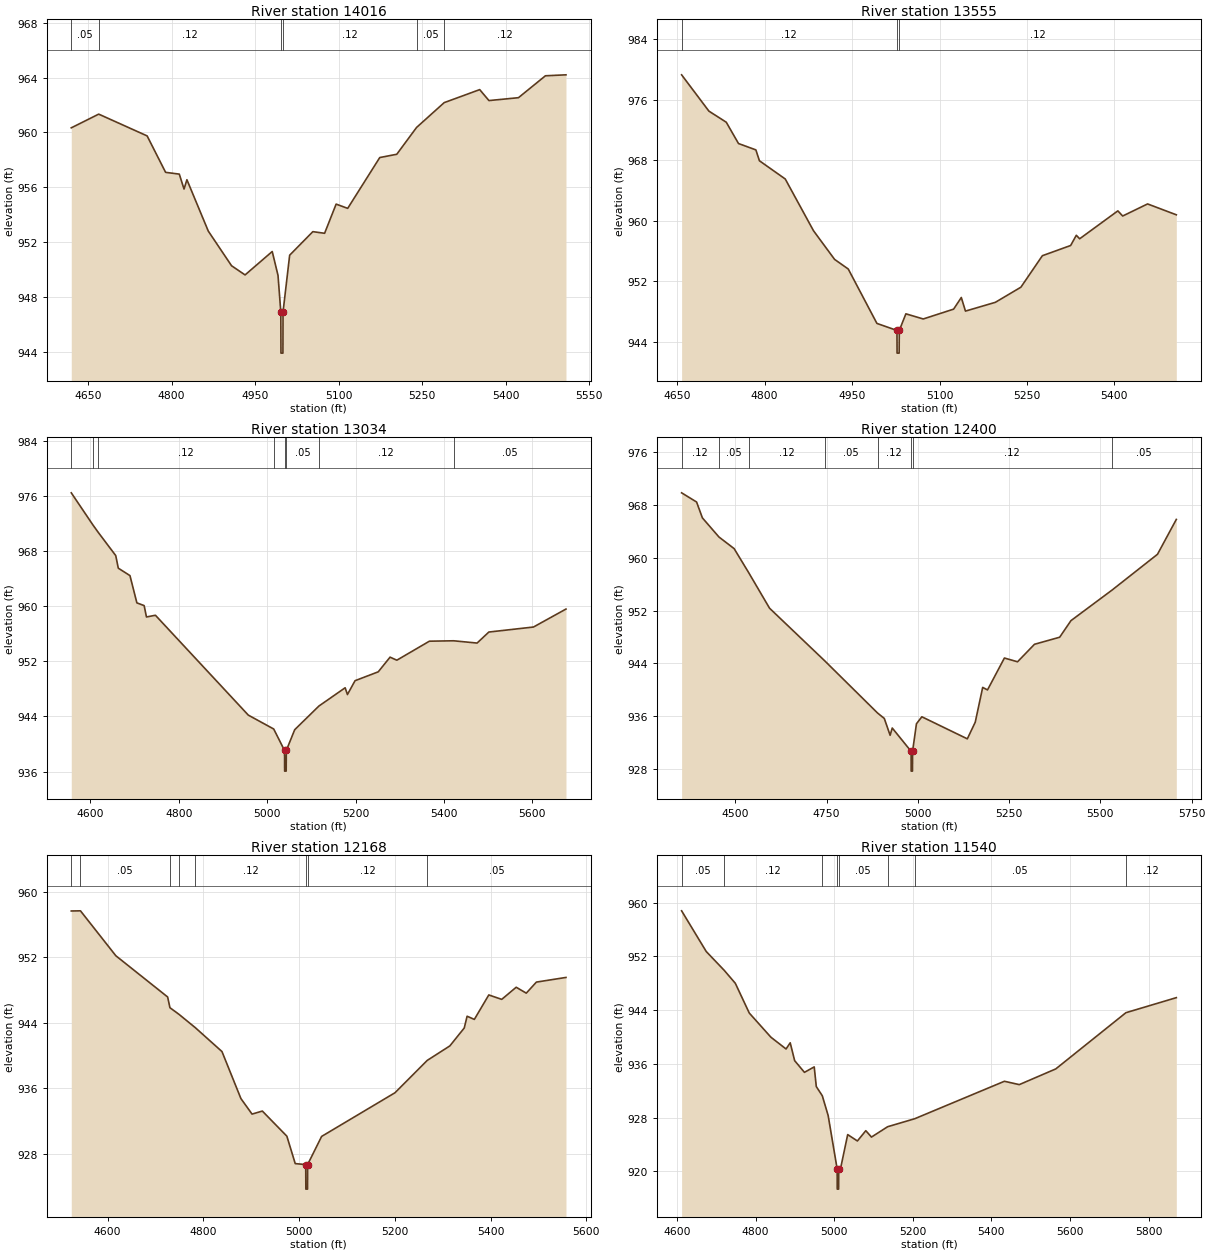
Type RM Length L Ch R = 1,14016,461,461,461
BEGIN DESCRIPTION:
SANDY 37 21.0
END DESCRIPTION:
XS GIS Cut Line= 3
      2890011.71     10186079.03      2890170.55     10185547.82
      2890058.56     10185232.68
#Sta/Elev= 30
  4619.6  960.34  4668.9  961.34  4755.9  959.75  4789.1  957.09  4813.7  956.96
  4822.2  955.87  4827.4  956.55  4865.8  952.80  4907.6  950.27  4931.9  949.60
  4980.7  951.31  4991.1  949.56  4996.1  946.89  4996.4  943.89  4999.9  943.89
  5000.1  946.89  5012.0  951.04  5053.7  952.76  5074.8  952.64  5095.5  954.77
  5116.3  954.46  5173.9  958.17  5204.5  958.41  5240.1  960.37  5289.7  962.18
  5353.5  963.13  5370.1  962.33  5423.1  962.54  5471.6  964.14  5508.5  964.21
#Mann=6,-1,0
  4619.6    0.05       0  4668.9    0.12       0  4996.1    0.07       0
  5000.1    0.12       0  5240.1    0.05       0  5289.7    0.12       0
Bank Sta=4996.1,5000.1
Exp/Cntr=0.3,0.1

Type RM Length L Ch R = 1,13555,521,521,521
BEGIN DESCRIPTION:
SANDY 37 20.0
END DESCRIPTION:
XS GIS Cut Line= 3
      2890714.85     10186099.94      2890451.80     10185714.49
      2890254.43     10185387.26
#Sta/Elev= 30
  4657.5  979.29  4704.3  974.49  4734.1  973.02  4755.1  970.20  4784.9  969.36
  4791.0  967.92  4835.3  965.51  4883.8  958.66  4920.0  954.87  4943.4  953.60
  4992.6  946.40  5027.0  945.47  5027.2  942.47  5030.7  942.47  5031.0  945.47
  5042.3  947.67  5072.1  946.99  5124.2  948.29  5137.4  949.83  5144.5  948.03
  5195.8  949.19  5239.6  951.19  5276.5  955.36  5325.0  956.71  5334.7  958.06
  5340.5  957.60  5406.0  961.29  5414.3  960.61  5457.0  962.21  5506.3  960.77
#Mann=3,-1,0
  4657.5    0.12       0  5027.0    0.07       0  5031.0    0.12       0
Bank Sta=5027,5031
Exp/Cntr=0.3,0.1

Type RM Length L Ch R = 1,13034,634,634,634
BEGIN DESCRIPTION:
SANDY 37 19.0
END DESCRIPTION:
XS GIS Cut Line= 3
      2891206.96     10185508.74      2890493.47     10185279.59
      2890141.86     10185164.99
#Sta/Elev= 30
  4556.7  976.50  4605.5  971.85  4618.1  970.72  4657.3  967.38  4663.1  965.55
  4689.5  964.47  4705.1  960.51  4721.6  960.11  4726.8  958.46  4747.1  958.71
  4957.2  944.20  5014.7  942.18  5039.2  939.06  5039.4  936.06  5042.9  936.06
  5043.2  939.06  5062.2  942.08  5117.0  945.52  5176.3  948.17  5181.5  947.19
  5198.7  949.20  5251.2  950.49  5277.9  952.62  5293.3  952.18  5366.9  954.94
  5421.7  955.00  5474.8  954.67  5501.4  956.27  5602.4  957.00  5675.9  959.61
#Mann=8,-1,0
  4556.7    0.12       0  4605.5    0.05       0  4618.1    0.12       0
  5014.7    0.05       0  5039.2    0.07       0  5043.2    0.05       0
  5117.0    0.12       0  5421.7    0.05       0
Bank Sta=5039.2,5043.2
Exp/Cntr=0.3,0.1

Type RM Length L Ch R = 1,12400,232,232,232
BEGIN DESCRIPTION:
SANDY 37 18.0
END DESCRIPTION:
XS GIS Cut Line= 3
      2891220.03     10185355.11      2890816.38     10184631.15
      2890305.67     10184503.11
#Sta/Elev= 30
  4352.6  969.83  4393.6  968.44  4409.6  966.03  4454.9  963.14  4496.5  961.38
  4536.7  957.71  4593.6  952.35  4745.0  944.37  4889.5  936.48  4907.9  935.66
  4923.9  933.11  4929.7  934.21  4981.4  930.68  4981.6  927.68  4985.1  927.68
  4985.4  930.68  4996.0  934.85  5010.8  935.91  5135.4  932.57  5157.1  935.09
  5177.5  940.36  5190.7  939.98  5237.0  944.81  5273.0  944.24  5319.4  946.89
  5388.4  947.96  5419.3  950.47  5531.9  955.10  5656.4  960.52  5708.0  965.80
#Mann=8,-1,0
  4352.6    0.12       0  4454.9    0.05       0  4536.7    0.12       0
  4745.0    0.05       0  4889.5    0.12       0  4981.4    0.07       0
  4985.4    0.12       0  5531.9    0.05       0
Bank Sta=4981.4,4985.4
Exp/Cntr=0.3,0.1

Type RM Length L Ch R = 1,12168,628,628,628
BEGIN DESCRIPTION:
Mapping XS d14a8f0d
END DESCRIPTION:
XS GIS Cut Line= 3
      2891235.67     10185217.13      2891076.80     10184641.57
      2890712.25     10184402.01
#Sta/Elev= 30
  4524.1  957.68  4543.3  957.70  4617.2  952.21  4725.4  947.17  4730.2  945.86
  4748.9  945.06  4783.4  943.41  4838.9  940.50  4878.4  934.76  4901.7  932.86
  4923.2  933.23  4974.4  930.16  4991.9  926.81  5013.8  926.69  5014.1  923.69
  5017.6  923.69  5017.8  926.69  5047.0  930.13  5200.3  935.47  5267.6  939.42
  5314.8  941.19  5344.9  943.38  5350.9  944.82  5366.0  944.43  5396.2  947.42
  5423.2  946.88  5453.4  948.36  5474.5  947.64  5495.6  948.99  5557.4  949.56
#Mann=8,-1,0
  4524.1    0.12       0  4543.3    0.05       0  4730.2    0.12       0
  4748.9    0.05       0  4783.4    0.12       0  5013.8    0.07       0
  5017.8    0.12       0  5267.6    0.05       0
Bank Sta=5013.8,5017.8
Exp/Cntr=0.3,0.1

Type RM Length L Ch R = 1,11540,195,195,195
BEGIN DESCRIPTION:
SANDY 37 17.0
END DESCRIPTION:
XS GIS Cut Line= 3
      2891954.37     10184737.91      2891256.49     10184474.90
      2890806.56     10184227.83
#Sta/Elev= 30
  4611.5  958.80  4674.2  952.74  4719.9  949.94  4748.2  948.01  4783.7  943.58
  4838.8  939.98  4877.3  938.23  4887.9  939.15  4899.2  936.49  4924.1  934.75
  4949.0  935.56  4954.3  932.63  4969.6  931.26  4984.5  928.31  5007.4  920.36
  5007.6  917.36  5011.1  917.36  5011.4  920.36  5016.2  920.48  5034.2  925.48
  5058.9  924.53  5080.3  926.06  5094.7  925.11  5135.8  926.65  5204.7  927.84
  5433.1  933.42  5470.9  932.92  5563.8  935.26  5742.3  943.63  5870.6  945.87
#Mann=8,-1,0
  4611.5    0.05       0  4719.9    0.12       0  4969.6    0.05       0
  5007.4    0.05       0  5011.4    0.05       0  5135.8    0.12       0
  5204.7    0.05       0  5742.3    0.12       0
Bank Sta=5007.4,5011.4
Exp/Cntr=0.3,0.1

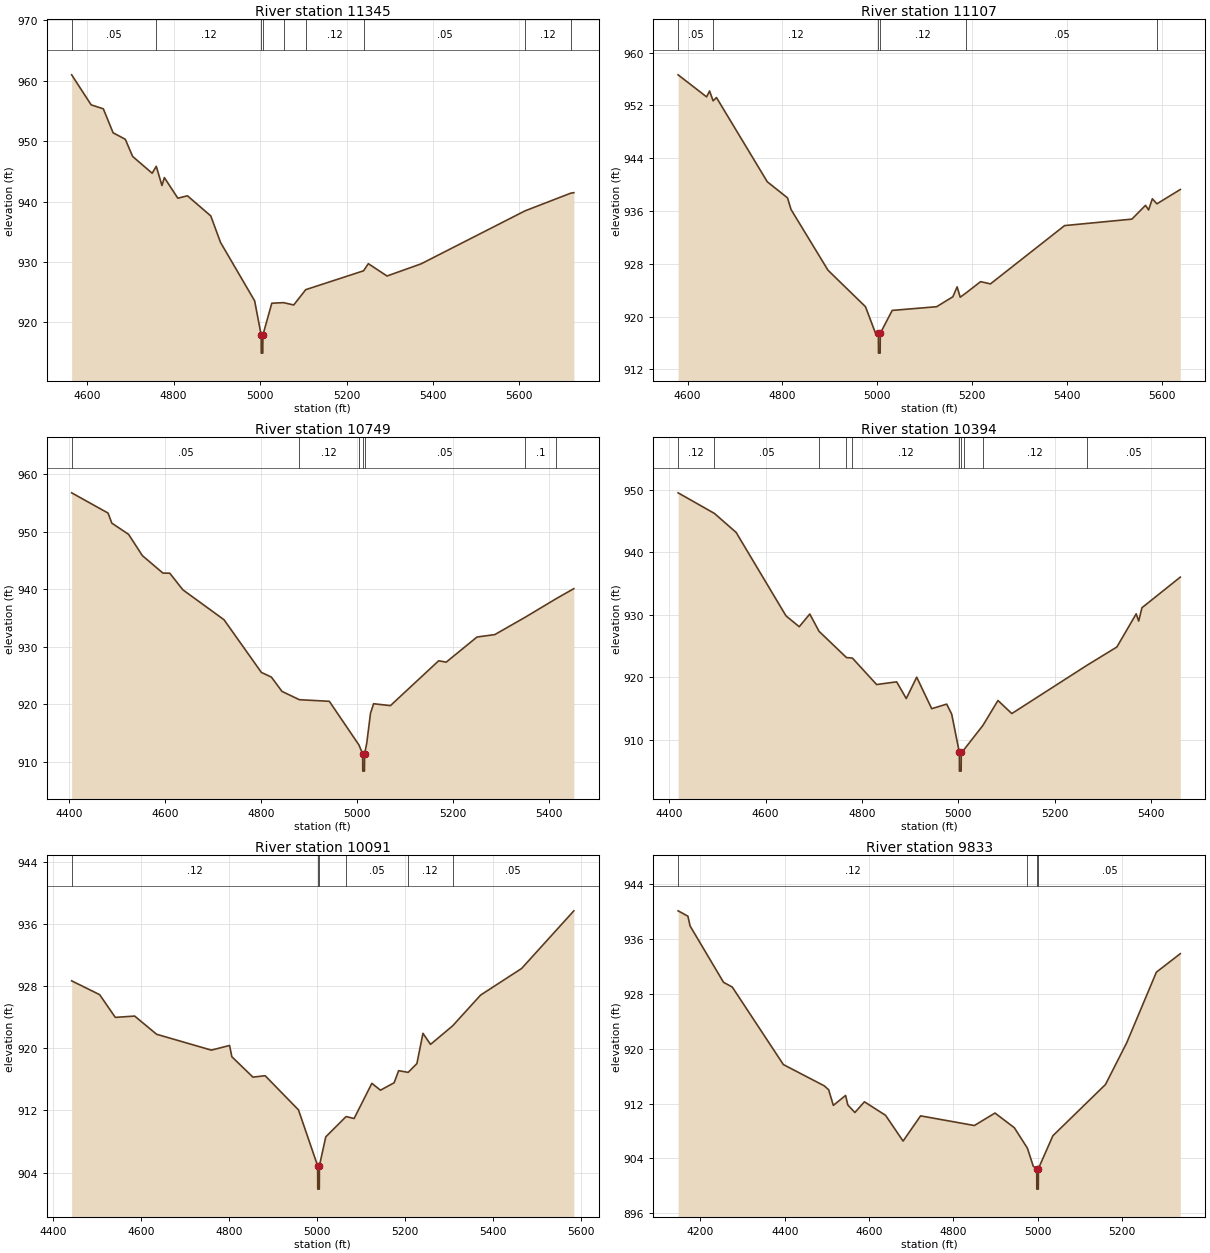
Type RM Length L Ch R = 1,11345,238,238,238
BEGIN DESCRIPTION:
SANDY 37 16.0
END DESCRIPTION:
XS GIS Cut Line= 3
      2892016.93     10184599.92      2891397.11     10184300.42
      2891022.08     10184011.34
#Sta/Elev= 30
  4564.0  960.96  4609.2  955.99  4637.3  955.34  4659.9  951.37  4688.1  950.30
  4705.1  947.46  4750.3  944.68  4759.8  945.83  4772.9  942.65  4778.5  943.96
  4809.7  940.55  4831.9  940.95  4885.9  937.62  4908.5  933.23  4987.4  923.57
  5002.5  917.92  5002.7  914.92  5006.2  914.92  5006.5  917.92  5027.1  923.18
  5054.2  923.27  5077.8  922.89  5105.6  925.42  5239.4  928.54  5250.4  929.72
  5293.7  927.68  5372.5  929.69  5613.1  938.46  5718.7  941.38  5725.9  941.46
#Mann=9,-1,0
  4564.0    0.05       0  4759.8    0.12       0  5002.5    0.07       0
  5006.5    0.12       0  5054.2    0.05       0  5105.6    0.12       0
  5239.4    0.05       0  5613.1    0.12       0  5718.7    0.05       0
Bank Sta=5002.5,5006.5
Exp/Cntr=0.3,0.1

Type RM Length L Ch R = 1,11107,358,358,358
BEGIN DESCRIPTION:
SANDY 37 15.0
END DESCRIPTION:
XS GIS Cut Line= 3
      2892056.00     10184446.28      2891592.43     10184097.30
      2891222.63     10183792.61
#Sta/Elev= 30
  4579.9  956.64  4640.0  953.30  4646.3  954.19  4653.7  952.70  4660.8  953.20
  4768.0  940.44  4810.7  938.00  4818.1  936.24  4896.1  927.04  4975.2  921.51
  4996.1  917.54  5002.4  917.48  5002.6  914.48  5006.1  914.48  5006.4  917.48
  5031.5  920.95  5125.2  921.51  5159.5  923.02  5168.5  924.52  5175.0  922.95
  5187.9  923.63  5218.0  925.31  5238.8  924.97  5395.2  933.80  5537.2  934.78
  5565.9  936.87  5572.4  936.17  5580.3  937.86  5590.0  937.10  5639.3  939.27
#Mann=6,-1,0
  4579.9    0.05       0  4653.7    0.12       0  5002.4    0.07       0
  5006.4    0.12       0  5187.9    0.05       0  5590.0     0.1       0
Bank Sta=5002.4,5006.4
Exp/Cntr=0.3,0.1

Type RM Length L Ch R = 1,10749,355,355,355
BEGIN DESCRIPTION:
SANDY 37 14.0
END DESCRIPTION:
XS GIS Cut Line= 3
      2892183.54     10184243.11      2891634.09     10183782.19
      2891349.19     10183613.84
#Sta/Elev= 30
  4404.7  956.71  4480.7  953.20  4488.5  951.46  4523.6  949.50  4552.3  945.82
  4595.2  942.79  4609.5  942.77  4636.8  939.89  4722.7  934.70  4800.7  925.56
  4821.6  924.75  4843.7  922.27  4879.9  920.83  4942.5  920.55  5004.3  912.98
  5012.1  911.44  5012.3  908.44  5015.8  908.44  5016.1  911.44  5020.6  913.30
  5028.4  918.47  5034.9  920.13  5070.0  919.80  5170.7  927.58  5186.4  927.34
  5250.7  931.70  5287.8  932.12  5351.7  935.15  5416.1  938.36  5452.8  940.09
#Mann=7,-1,0
  4404.7    0.05       0  4879.9    0.12       0  5004.3    0.05       0
  5012.1    0.07       0  5016.1    0.05       0  5351.7     0.1       0
  5416.1    0.05       0
Bank Sta=5012.1,5016.1
Exp/Cntr=0.3,0.1

Type RM Length L Ch R = 1,10394,303,303,303
BEGIN DESCRIPTION:
Mapping XS 5a632ff5
END DESCRIPTION:
XS GIS Cut Line= 3
      2892308.59     10183933.27      2892147.11     10183636.36
      2891469.02     10183444.10
#Sta/Elev= 30
  4418.2  949.48  4493.6  946.19  4538.7  943.15  4642.2  929.82  4669.7  928.08
  4691.6  930.11  4710.8  927.35  4767.8  923.15  4780.1  923.07  4830.4  918.84
  4872.0  919.27  4892.0  916.60  4913.6  920.02  4944.8  914.98  4975.9  915.71
  4986.3  914.11  5002.2  908.00  5002.4  905.00  5005.9  905.00  5006.2  908.00
  5011.9  908.44  5051.2  912.32  5082.4  916.29  5111.1  914.20  5266.5  921.88
  5329.3  924.84  5369.4  930.14  5374.6  928.98  5381.3  931.11  5461.0  936.01
#Mann=10,-1,0
  4418.2    0.12       0  4493.6    0.05       0  4710.8    0.12       0
  4767.8    0.05       0  4780.1    0.12       0  5002.2    0.07       0
  5006.2    0.12       0  5011.9    0.05       0  5051.2    0.12       0
  5266.5    0.05       0
Bank Sta=5002.2,5006.2
Exp/Cntr=0.3,0.1

Type RM Length L Ch R = 1,10091,258,258,258
BEGIN DESCRIPTION:
SANDY 37 13.0
END DESCRIPTION:
XS GIS Cut Line= 3
      2892326.78     10183607.67      2892154.93     10183326.47
      2891371.04     10183120.73
#Sta/Elev= 30
  4442.8  928.67  4506.4  926.89  4541.9  923.97  4585.8  924.14  4635.7  921.80
  4760.0  919.76  4801.3  920.36  4806.5  918.91  4854.3  916.29  4882.1  916.47
  4957.7  912.08  5001.2  904.89  5001.5  901.89  5005.0  901.89  5005.2  904.89
  5019.7  908.61  5065.8  911.22  5084.0  910.97  5124.3  915.49  5143.8  914.61
  5174.8  915.56  5185.1  917.12  5206.8  916.90  5226.5  918.03  5240.3  921.92
  5257.5  920.50  5307.4  922.87  5371.2  926.84  5464.3  930.26  5582.8  937.67
#Mann=6,-1,0
  4442.8    0.12       0  5001.2    0.07       0  5005.2    0.12       0
  5065.8    0.05       0  5206.8    0.12       0  5307.4    0.05       0
Bank Sta=5001.2,5005.2
Exp/Cntr=0.3,0.1

Type RM Length L Ch R = 1,9833,631,631,631
BEGIN DESCRIPTION:
SANDY 37 12.0
END DESCRIPTION:
XS GIS Cut Line= 3
      2892829.44     10183235.33      2892097.63     10183032.19
      2891669.35     10182985.47
#Sta/Elev= 30
  4147.3  940.13  4170.5  939.35  4175.7  937.92  4255.0  929.70  4275.7  929.01
  4396.8  917.70  4493.7  914.60  4504.1  914.03  4515.2  911.75  4544.3  913.20
  4549.5  911.81  4566.3  910.71  4588.9  912.27  4639.0  910.30  4680.5  906.54
  4722.0  910.22  4849.5  908.81  4898.4  910.63  4944.2  908.49  4975.2  905.51
  4989.2  902.85  4997.3  902.53  4997.5  899.53  5001.0  899.53  5001.3  902.53
  5035.6  907.32  5160.2  914.79  5210.5  920.87  5280.9  931.18  5337.6  933.88
#Mann=4,-1,0
  4147.3    0.12       0  4975.2    0.05       0  4997.3    0.05       0
  5001.3    0.05       0
Bank Sta=4997.3,5001.3
Exp/Cntr=0.3,0.1

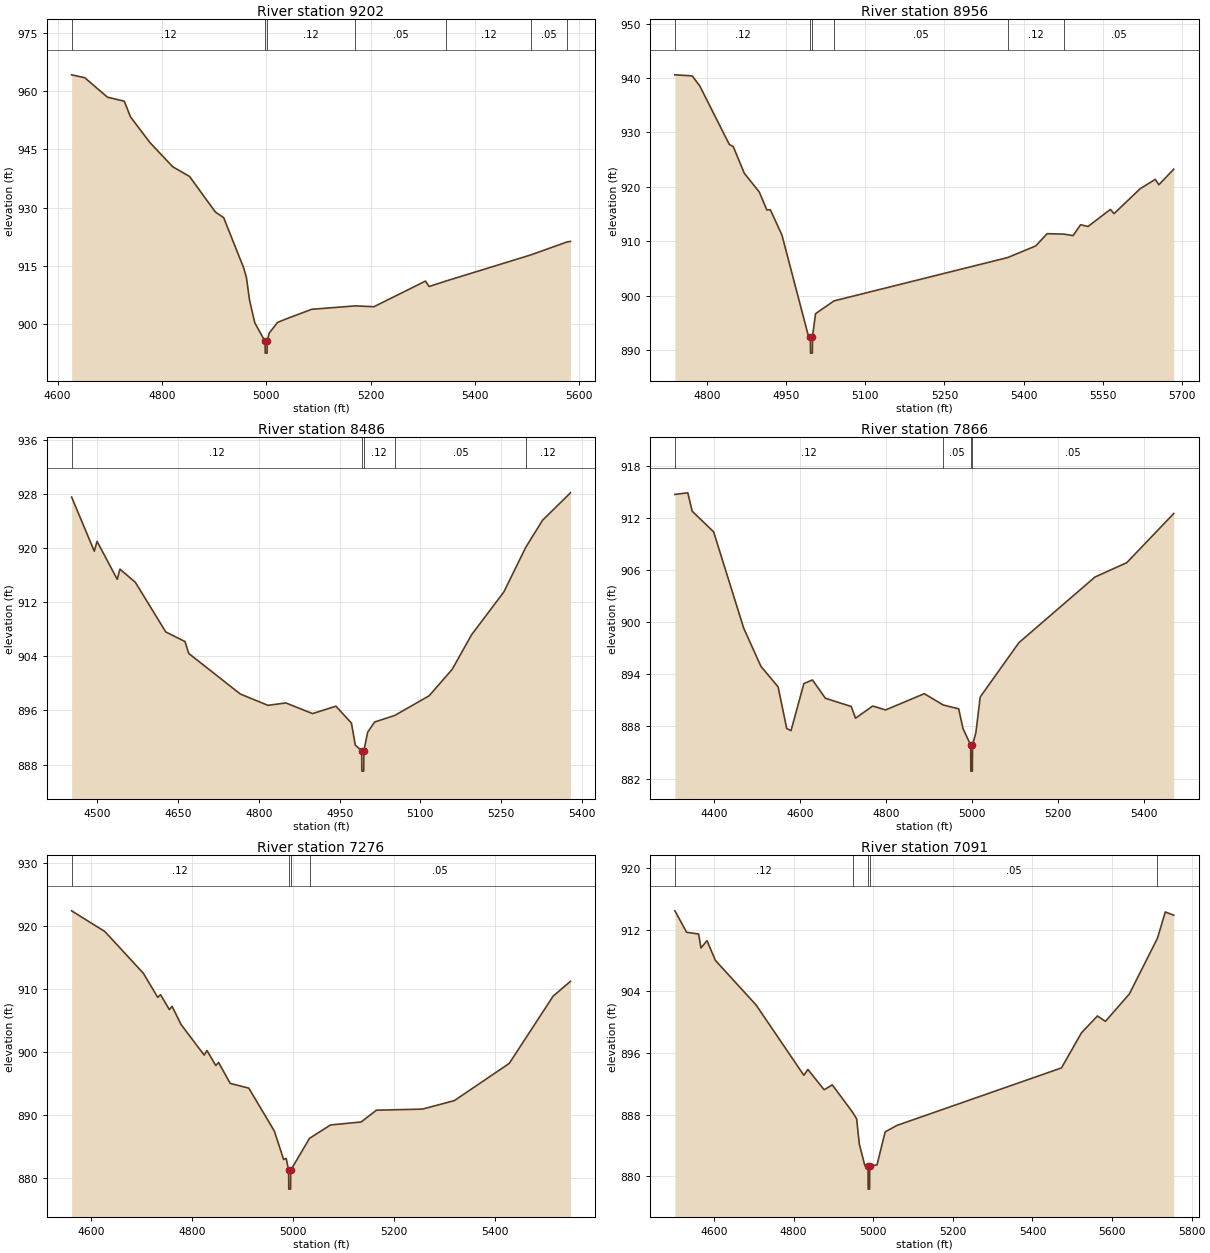
Type RM Length L Ch R = 1,9202,246,246,246
BEGIN DESCRIPTION:
SANDY 37 11.0
END DESCRIPTION:
XS GIS Cut Line= 3
      2892524.68     10182277.01      2891993.47     10182568.65
      2891749.70     10182820.21
#Sta/Elev= 30
  4626.7  964.16  4651.9  963.42  4695.5  958.41  4727.7  957.38  4739.6  953.35
  4777.0  946.72  4820.6  940.52  4852.8  938.04  4902.1  928.92  4918.2  927.44
  4956.1  914.68  4961.8  912.09  4967.8  906.23  4977.9  900.38  4997.7  895.61
  4997.9  892.61  5001.4  892.61  5001.7  895.61  5005.4  897.75  5021.5  900.50
  5036.2  901.31  5086.9  903.88  5170.9  904.76  5206.2  904.54  5305.1  911.13
  5312.0  909.74  5344.9  911.17  5507.4  917.88  5576.4  921.19  5583.0  921.33
#Mann=7,-1,0
  4626.7    0.12       0  4997.7    0.07       0  5001.7    0.12       0
  5170.9    0.05       0  5344.9    0.12       0  5507.4    0.05       0
  5576.4    0.12       0
Bank Sta=4997.7,5001.7
Exp/Cntr=0.3,0.1

Type RM Length L Ch R = 1,8956,470,470,470
BEGIN DESCRIPTION:
SANDY 37 10.0
END DESCRIPTION:
XS GIS Cut Line= 3
      2892183.56     10182105.13      2891850.24     10182500.94
      2891559.90     10182817.21
#Sta/Elev= 30
  4738.4  940.60  4771.2  940.41  4785.5  938.57  4841.5  927.81  4849.2  927.38
  4870.0  922.51  4898.6  919.03  4912.9  915.74  4919.5  915.78  4941.5  911.13
  4991.0  892.84  4995.5  892.40  4995.8  889.40  4999.3  889.40  4999.5  892.40
  5005.3  896.66  5040.3  899.01  5369.9  906.98  5423.2  909.12  5444.8  911.37
  5476.3  911.30  5494.1  911.02  5508.3  913.02  5522.4  912.70  5565.0  915.84
  5571.8  915.06  5621.7  919.67  5650.1  921.36  5656.9  920.38  5685.2  923.24
#Mann=6,-1,0
  4738.4    0.12       0  4995.5    0.07       0  4999.5    0.12       0
  5040.3    0.05       0  5369.9    0.12       0  5476.3    0.05       0
Bank Sta=4995.5,4999.5
Exp/Cntr=0.3,0.1

Type RM Length L Ch R = 1,8486,620,620,620
BEGIN DESCRIPTION:
SANDY 37 9.0
END DESCRIPTION:
XS GIS Cut Line= 3
      2892050.78     10181998.34      2891626.28     10182097.30
      2891355.45     10182506.15
#Sta/Elev= 30
  4452.3  927.53  4494.4  919.53  4499.6  920.98  4537.0  915.38  4542.1  916.87
  4570.5  914.95  4627.2  907.60  4662.9  906.18  4669.8  904.42  4765.6  898.43
  4816.9  896.76  4850.3  897.11  4899.7  895.54  4943.1  896.63  4971.9  894.14
  4979.1  890.88  4991.0  890.04  4991.2  887.04  4994.7  887.04  4995.0  890.04
  5002.0  892.79  5015.1  894.30  5052.5  895.27  5116.3  898.18  5159.0  902.08
  5195.0  907.19  5254.7  913.48  5295.7  920.12  5326.9  924.11  5378.6  928.15
#Mann=5,-1,0
  4452.3    0.12       0  4991.0    0.07       0  4995.0    0.12       0
  5052.5    0.05       0  5295.7    0.12       0
Bank Sta=4991,4995
Exp/Cntr=0.3,0.1

Type RM Length L Ch R = 1,7866,590,590,590
BEGIN DESCRIPTION:
SANDY 37 8.0
END DESCRIPTION:
XS GIS Cut Line= 3
      2891855.73     10181753.11      2891076.80     10181771.78
      2890696.64     10181803.02
#Sta/Elev= 30
  4308.0  914.70  4338.1  914.88  4348.1  912.77  4398.1  910.39  4468.1  899.30
  4508.1  894.92  4548.1  892.55  4568.1  887.76  4578.1  887.52  4608.1  892.94
  4628.1  893.35  4658.1  891.24  4718.2  890.30  4728.2  888.95  4768.2  890.35
  4798.2  889.90  4888.2  891.77  4932.2  890.47  4968.2  890.03  4978.2  887.76
  4996.2  885.86  4996.4  882.86  5000.0  882.86  5000.3  885.86  5008.2  887.28
  5018.3  891.39  5108.3  897.64  5285.2  905.19  5359.2  906.84  5468.6  912.50
#Mann=4,-1,0
  4308.0    0.12       0  4932.2    0.05       0  4996.2    0.05       0
  5000.3    0.05       0
Bank Sta=4996.2,5000.3
Exp/Cntr=0.3,0.1

Type RM Length L Ch R = 1,7276,185,185,185
BEGIN DESCRIPTION:
SANDY 37 7.0
END DESCRIPTION:
XS GIS Cut Line= 3
      2891855.48     10181649.40      2891542.95     10181506.15
      2890905.68     10181603.11
#Sta/Elev= 30
  4561.5  922.44  4627.3  919.16  4703.7  912.52  4732.2  908.69  4737.7  909.12
  4755.2  906.75  4760.7  907.26  4778.2  904.40  4824.2  899.52  4829.7  900.25
  4847.2  897.86  4852.7  898.36  4875.7  895.03  4912.6  894.27  4963.2  887.46
  4981.6  882.93  4986.7  883.11  4991.5  881.23  4991.8  878.23  4995.4  878.23
  4995.6  881.23  5032.9  886.30  5074.5  888.42  5135.2  888.90  5165.5  890.77
  5256.6  890.94  5319.8  892.29  5428.5  898.19  5515.6  908.89  5549.9  911.24
#Mann=4,-1,0
  4561.5    0.12       0  4991.5    0.07       0  4995.6    0.12       0
  5032.9    0.05       0
Bank Sta=4991.5,4995.6
Exp/Cntr=0.3,0.1

Type RM Length L Ch R = 1,7091,499,499,499
BEGIN DESCRIPTION:
SANDY 37 6.0
END DESCRIPTION:
XS GIS Cut Line= 4
      2891897.12     10181553.03      2891631.72     10181378.36
      2891323.82     10181313.68      2890704.42     10181360.32
#Sta/Elev= 30
  4501.6  914.48  4531.0  911.69  4561.2  911.47  4567.1  909.65  4582.2  910.61
  4603.3  908.04  4705.7  902.24  4825.6  893.11  4835.7  893.87  4876.6  891.23
  4897.0  891.87  4948.1  888.31  4958.3  887.44  4964.9  884.19  4978.8  881.38
  4986.9  881.32  4987.2  878.32  4990.8  878.32  4991.0  881.32  5009.4  881.46
  5029.9  885.76  5059.6  886.60  5473.0  894.07  5523.2  898.63  5563.3  900.82
  5583.4  900.12  5643.5  903.68  5714.1  910.92  5733.8  914.33  5755.1  913.91
#Mann=5,-1,0
  4501.6    0.12       0  4948.1    0.05       0  4986.9    0.05       0
  4991.0    0.05       0  5714.1    0.12       0
Bank Sta=4986.9,4991
Exp/Cntr=0.3,0.1

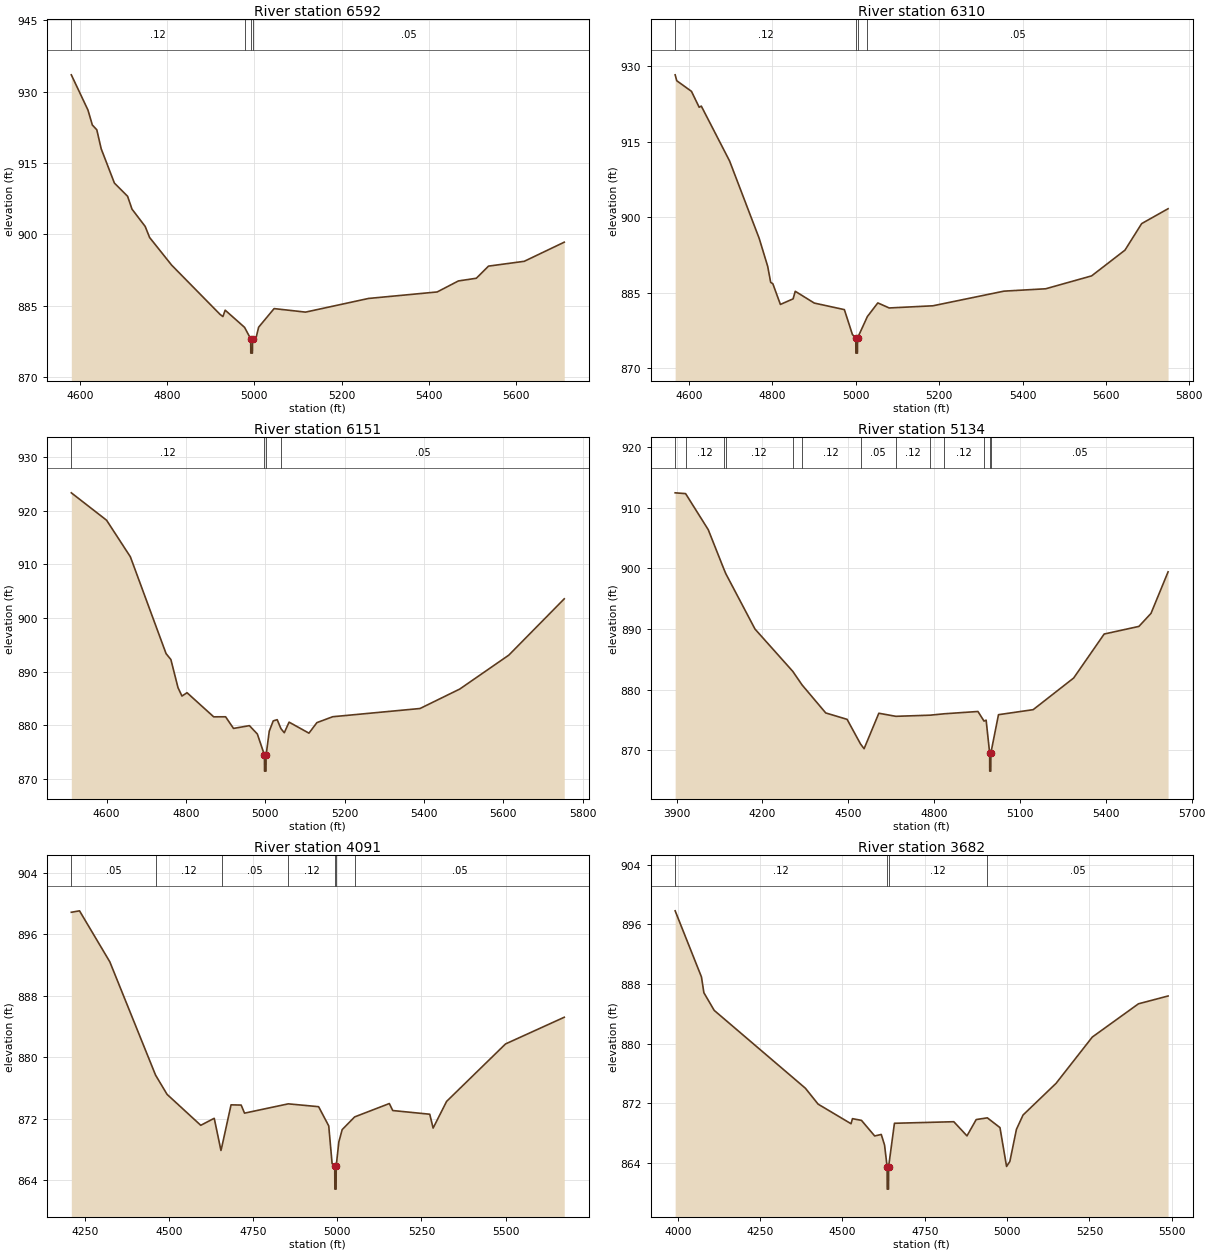
Type RM Length L Ch R = 1,6592,282,282,282
BEGIN DESCRIPTION:
SANDY 37 5.0
END DESCRIPTION:
XS GIS Cut Line= 3
      2891933.53     10180805.64      2891607.99     10180853.14
      2890830.06     10181050.26
#Sta/Elev= 30
  4579.7  933.56  4617.9  926.16  4628.0  923.01  4638.2  922.01  4648.3  918.01
  4678.6  910.81  4708.9  908.03  4719.0  905.33  4749.3  901.69  4759.4  899.37
  4810.0  893.56  4921.4  883.18  4927.7  882.75  4932.9  884.09  4977.4  880.48
  4991.5  878.06  4991.7  875.06  4995.4  875.06  4995.7  878.06  5003.9  878.33
  5009.7  880.51  5045.2  884.42  5117.4  883.68  5261.8  886.55  5419.6  887.92
  5468.1  890.23  5509.4  890.80  5537.4  893.35  5619.4  894.36  5711.2  898.38
#Mann=4,-1,0
  4579.7    0.12       0  4977.4    0.05       0  4991.5    0.05       0
  4995.7    0.05       0
Bank Sta=4991.5,4995.7
Exp/Cntr=0.3,0.1

Type RM Length L Ch R = 1,6310,159,159,159
BEGIN DESCRIPTION:
SANDY 37 4.0
END DESCRIPTION:
XS GIS Cut Line= 3
      2891884.14     10180537.39      2891243.47     10180651.99
      2890712.27     10180644.17
#Sta/Elev= 30
  4567.0  928.32  4570.8  927.15  4606.1  925.04  4624.6  921.88  4629.7  922.11
  4697.5  911.22  4768.6  895.82  4788.9  890.29  4796.1  887.10  4801.2  886.84
  4819.4  882.72  4849.9  883.83  4855.0  885.33  4900.7  882.99  4972.8  881.69
  4992.1  876.75  5000.2  876.05  5000.4  873.05  5004.1  873.05  5004.4  876.05
  5028.0  880.32  5053.0  883.02  5080.3  882.02  5185.1  882.45  5355.6  885.36
  5455.6  885.83  5565.7  888.39  5645.7  893.50  5685.7  898.77  5749.1  901.73
#Mann=4,-1,0
  4567.0    0.12       0  5000.2    0.07       0  5004.4    0.12       0
  5028.0    0.05       0
Bank Sta=5000.2,5004.4
Exp/Cntr=0.3,0.1

Type RM Length L Ch R = 1,6151,1017,1017,1017
BEGIN DESCRIPTION:
SANDY 37 3.0
END DESCRIPTION:
XS GIS Cut Line= 3
      2891894.55     10180451.46      2891602.84     10180459.28
      2890652.35     10180493.13
#Sta/Elev= 30
  4510.9  923.30  4599.8  918.20  4659.8  911.39  4749.8  893.37  4762.0  892.25
  4779.9  887.03  4789.9  885.46  4802.7  886.08  4869.9  881.59  4899.9  881.60
  4919.9  879.43  4960.0  879.95  4980.0  878.39  4997.9  874.48  4998.1  871.48
  5001.8  871.48  5002.1  874.48  5010.0  878.91  5020.0  880.83  5030.0  881.06
  5039.5  879.39  5047.9  878.63  5060.0  880.60  5110.1  878.55  5130.1  880.51
  5170.1  881.61  5390.2  883.14  5490.3  886.76  5614.1  893.08  5753.8  903.56
#Mann=4,-1,0
  4510.9    0.12       0  4997.9    0.07       0  5002.1    0.12       0
  5039.5    0.05       0
Bank Sta=4997.9,5002.1
Exp/Cntr=0.3,0.1

Type RM Length L Ch R = 1,5134,1043,1043,1043
BEGIN DESCRIPTION:
Mapping XS 5bd05bf3
END DESCRIPTION:
XS GIS Cut Line= 3
      2892075.54     10179480.23      2891381.04     10179657.40
      2890599.33     10180290.55
#Sta/Elev= 30
  3894.9  912.49  3931.4  912.36  4010.6  906.40  4064.5  899.98  4071.9  899.14
  4174.0  889.99  4306.1  883.00  4338.4  880.77  4421.1  876.14  4495.8  875.08
  4542.7  871.02  4555.2  870.23  4606.7  876.09  4666.2  875.58  4786.1  875.77
  4835.6  876.00  4953.1  876.38  4974.4  874.79  4981.7  874.95  4994.0  869.53
  4994.3  866.53  4998.0  866.53  4998.3  869.53  5024.9  875.85  5146.1  876.68
  5287.7  881.91  5394.2  889.17  5515.7  890.43  5557.9  892.58  5617.6  899.44
#Mann=13,-1,0
  3894.9    0.05       0  3931.4    0.12       0  4064.5    0.05       0
  4071.9    0.12       0  4306.1    0.05       0  4338.4    0.12       0
  4542.7    0.05       0  4666.2    0.12       0  4786.1    0.05       0
  4835.6    0.12       0  4974.4    0.05       0  4994.0    0.05       0
  4998.3    0.05       0
Bank Sta=4994,4998.3
Exp/Cntr=0.3,0.1

Type RM Length L Ch R = 1,4091,409,409,409
BEGIN DESCRIPTION:
Mapping XS 60e3b412
END DESCRIPTION:
XS GIS Cut Line= 3
      2891870.02     10179395.18      2890700.69     10179331.40
      2890438.51     10179196.76
#Sta/Elev= 30
  4208.7  898.86  4233.1  899.05  4323.2  892.42  4459.3  877.68  4493.5  875.18
  4593.6  871.16  4633.7  872.07  4653.7  867.89  4656.6  868.41  4683.7  873.82
  4713.8  873.79  4723.8  872.74  4853.9  873.95  4944.1  873.58  4974.2  871.08
  4984.2  866.18  4992.1  865.86  4992.4  862.86  4996.1  862.86  4996.4  865.86
  5004.2  868.99  5014.2  870.60  5051.2  872.25  5154.4  873.99  5164.5  873.08
  5274.6  872.60  5284.6  870.80  5324.7  874.27  5499.9  881.74  5674.5  885.21
#Mann=7,-1,0
  4208.7    0.05       0  4459.3    0.12       0  4656.6    0.05       0
  4853.9    0.12       0  4992.1    0.07       0  4996.4    0.12       0
  5051.2    0.05       0
Bank Sta=4992.1,4996.4
Exp/Cntr=0.3,0.1

Type RM Length L Ch R = 1,3682,696,696,696
BEGIN DESCRIPTION:
Mapping XS ceb46475
END DESCRIPTION:
XS GIS Cut Line= 3
      2892029.47     10179140.04      2891512.15     10178987.68
      2890555.83     10178938.09
#Sta/Elev= 30
  3991.9  897.82  4071.8  888.95  4079.2  886.83  4110.5  884.47  4387.4  874.03
  4426.0  871.90  4526.0  869.27  4530.4  869.95  4557.7  869.72  4597.8  867.63
  4617.8  867.83  4627.8  866.41  4635.6  863.50  4635.9  860.50  4639.8  860.50
  4640.1  863.50  4657.8  869.33  4838.1  869.54  4878.1  867.64  4906.1  869.83
  4939.9  870.06  4978.3  868.75  4998.3  863.54  5008.3  864.21  5028.3  868.52
  5048.4  870.44  5148.5  874.68  5258.6  880.89  5398.8  885.35  5488.8  886.40
#Mann=4,-1,0
  3991.9    0.12       0  4635.6    0.05       0  4640.1    0.12       0
  4939.9    0.05       0
Bank Sta=4635.6,4640.1
Exp/Cntr=0.3,0.1

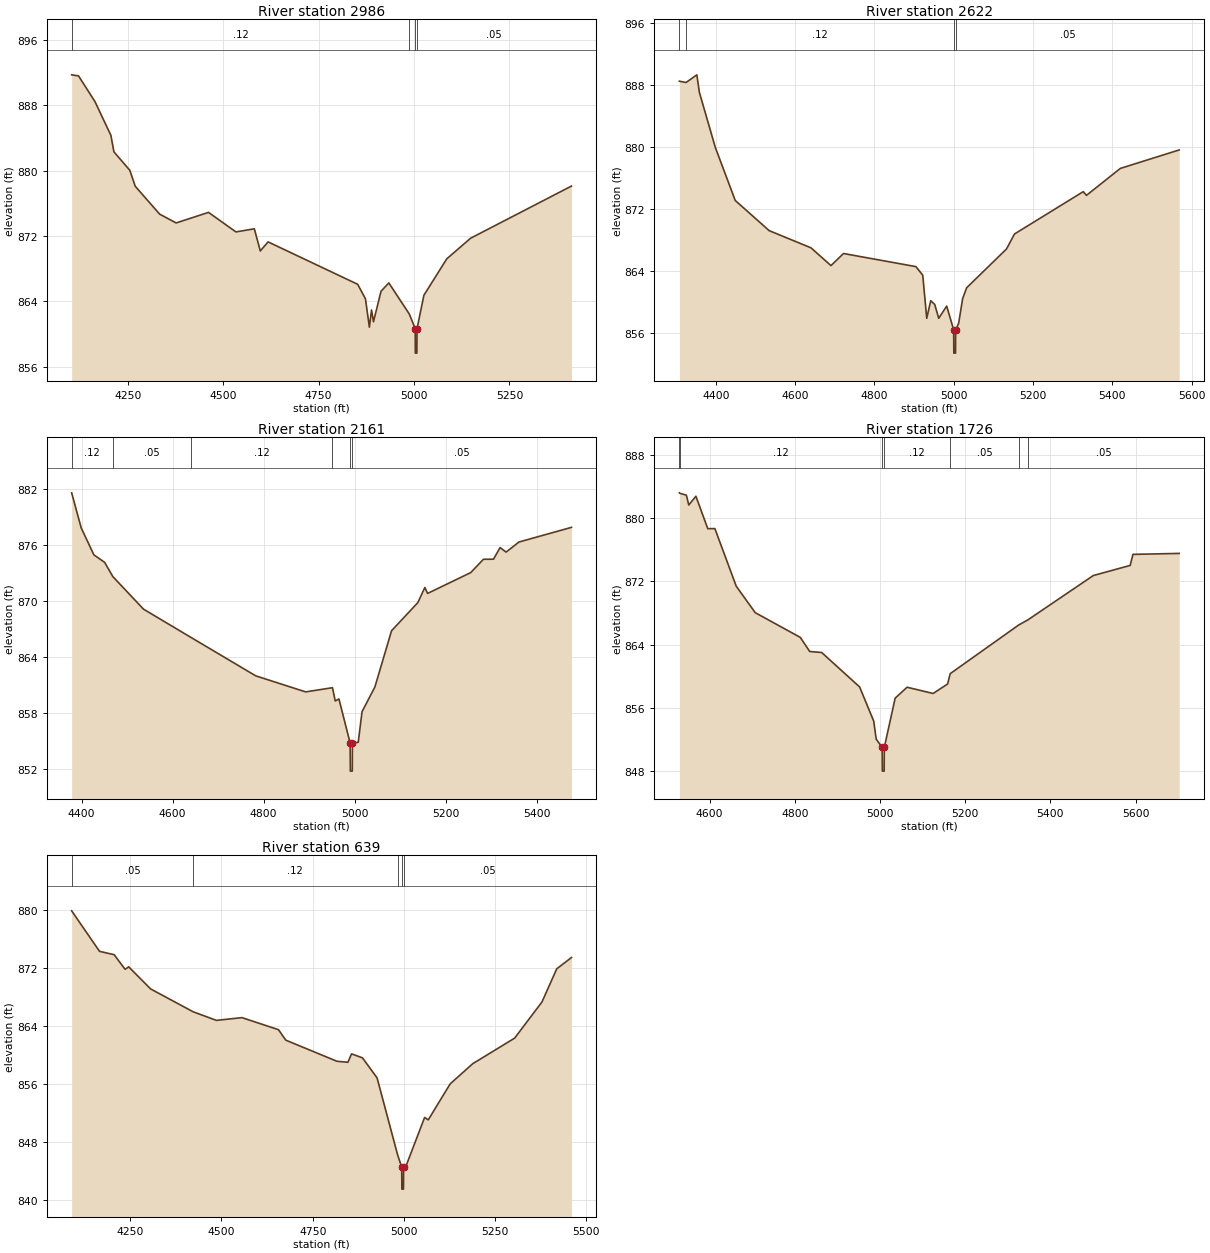
Type RM Length L Ch R = 1,2986,364,364,364
BEGIN DESCRIPTION:
Mapping XS 734a515c
END DESCRIPTION:
XS GIS Cut Line= 4
      2892033.07     10178870.76      2891660.98     10178569.54
      2891086.93     10178452.61      2890842.44     10178470.33
#Sta/Elev= 30
  4103.0  891.73  4121.0  891.60  4164.0  888.46  4205.8  884.33  4213.7  882.31
  4255.4  880.05  4269.7  878.09  4333.7  874.68  4376.8  873.61  4461.6  874.90
  4533.5  872.51  4581.7  872.89  4597.3  870.18  4617.7  871.29  4852.5  866.10
  4872.9  864.32  4883.1  860.86  4888.8  862.96  4893.9  861.52  4913.7  865.25
  4934.1  866.27  4987.8  862.46  5003.2  860.68  5003.5  857.68  5007.6  857.68
  5008.0  860.68  5026.0  864.76  5086.0  869.22  5148.4  871.74  5412.7  878.12
#Mann=4,-1,0
  4103.0    0.12       0  4987.8    0.05       0  5003.2    0.05       0
  5008.0    0.05       0
Bank Sta=5003.2,5008
Exp/Cntr=0.3,0.1

Type RM Length L Ch R = 1,2622,461,461,461
BEGIN DESCRIPTION:
Mapping XS 23d136e6
END DESCRIPTION:
XS GIS Cut Line= 3
      2891965.75     10178073.45      2890994.80     10178179.76
      2890729.07     10178278.97
#Sta/Elev= 30
  4308.3  888.52  4325.1  888.35  4352.4  889.34  4358.7  887.09  4398.9  879.98
  4449.2  873.13  4534.8  869.24  4640.3  867.02  4690.6  864.73  4722.2  866.29
  4904.7  864.60  4922.0  863.50  4932.1  857.93  4942.1  860.20  4952.2  859.72
  4962.3  857.93  4982.4  859.51  5000.0  856.44  5000.4  853.44  5004.6  853.44
  5005.0  856.44  5012.6  857.29  5022.6  860.47  5032.7  861.87  5133.3  866.88
  5153.4  868.81  5326.8  874.27  5334.8  873.79  5420.4  877.27  5568.7  879.65
#Mann=4,-1,0
  4308.3    0.05       0  4325.1    0.12       0  5000.0    0.07       0
  5005.0    0.05       0
Bank Sta=5000,5005
Exp/Cntr=0.3,0.1

Type RM Length L Ch R = 1,2161,435,435,435
BEGIN DESCRIPTION:
Mapping XS e5437b46
END DESCRIPTION:
XS GIS Cut Line= 3
      2891597.22     10177446.24      2890863.69     10177903.37
      2890714.88     10178084.07
#Sta/Elev= 30
  4378.1  881.60  4399.1  877.84  4427.0  874.95  4450.6  874.15  4468.7  872.62
  4535.9  869.14  4640.9  866.09  4782.6  861.99  4892.3  860.27  4951.3  860.72
  4957.3  859.30  4965.5  859.51  4990.1  854.78  4990.5  851.78  4994.8  851.78
  4995.1  854.78  5007.9  854.87  5016.2  858.14  5044.5  860.80  5081.1  866.82
  5138.9  869.84  5154.3  871.46  5160.2  870.82  5255.0  873.05  5283.0  874.48
  5305.2  874.49  5319.6  875.73  5332.8  875.25  5361.2  876.33  5476.5  877.90
#Mann=6,-1,0
  4378.1    0.12       0  4468.7    0.05       0  4640.9    0.12       0
  4951.3    0.05       0  4990.1    0.05       0  4995.1    0.05       0
Bank Sta=4990.1,4995.1
Exp/Cntr=0.3,0.1

Type RM Length L Ch R = 1,1726,1087,1087,1087
BEGIN DESCRIPTION:
Mapping XS 961fbd20
END DESCRIPTION:
XS GIS Cut Line= 3
      2891352.67     10177159.24      2890792.82     10177442.71
      2890523.52     10177917.53
#Sta/Elev= 30
  4529.0  883.22  4529.9  883.17  4545.5  882.92  4551.1  881.68  4567.8  882.79
  4595.7  878.68  4612.4  878.69  4662.5  871.40  4707.1  868.05  4812.9  864.92
  4835.1  863.13  4863.0  863.01  4952.1  858.65  4985.2  854.33  4991.1  852.04
  5005.1  850.99  5005.5  847.99  5009.8  847.99  5010.1  850.99  5035.6  857.23
  5063.6  858.61  5124.7  857.82  5158.7  859.02  5164.9  860.33  5325.9  866.50
  5346.7  867.12  5500.8  872.75  5587.3  874.03  5593.8  875.43  5702.4  875.55
#Mann=7,-1,0
  4529.0    0.05       0  4529.9    0.12       0  5005.1    0.07       0
  5010.1    0.12       0  5164.9    0.05       0  5325.9    0.12       0
  5346.7    0.05       0
Bank Sta=5005.1,5010.1
Exp/Cntr=0.3,0.1

Type RM Length L Ch R = 1,639,0,0,0
BEGIN DESCRIPTION:
SANDY 37 1.0
END DESCRIPTION:
XS GIS Cut Line= 3
      2891171.98     10176868.67      2890093.95     10176822.79
      2889828.84     10176942.04
#Sta/Elev= 30
  4089.4  879.84  4165.8  874.26  4205.8  873.80  4235.8  871.79  4245.8  872.12
  4305.9  869.08  4422.2  865.94  4486.1  864.75  4556.1  865.13  4656.2  863.47
  4676.2  862.03  4816.3  859.12  4846.4  858.98  4856.4  860.14  4886.4  859.59
  4926.4  856.83  4982.4  846.28  4993.9  844.51  4994.3  841.51  4998.7  841.51
  4999.1  844.51  5006.5  844.80  5056.6  851.38  5066.6  851.05  5126.6  856.00
  5188.4  858.78  5303.4  862.31  5378.4  867.30  5418.7  871.85  5459.1  873.41
#Mann=5,-1,0
  4089.4    0.05       0  4422.2    0.12       0  4982.4    0.05       0
  4993.9    0.05       0  4999.1    0.05       0
Bank Sta=4993.9,4999.1
Exp/Cntr=0.3,0.1

Chan Stop Cuts=-1