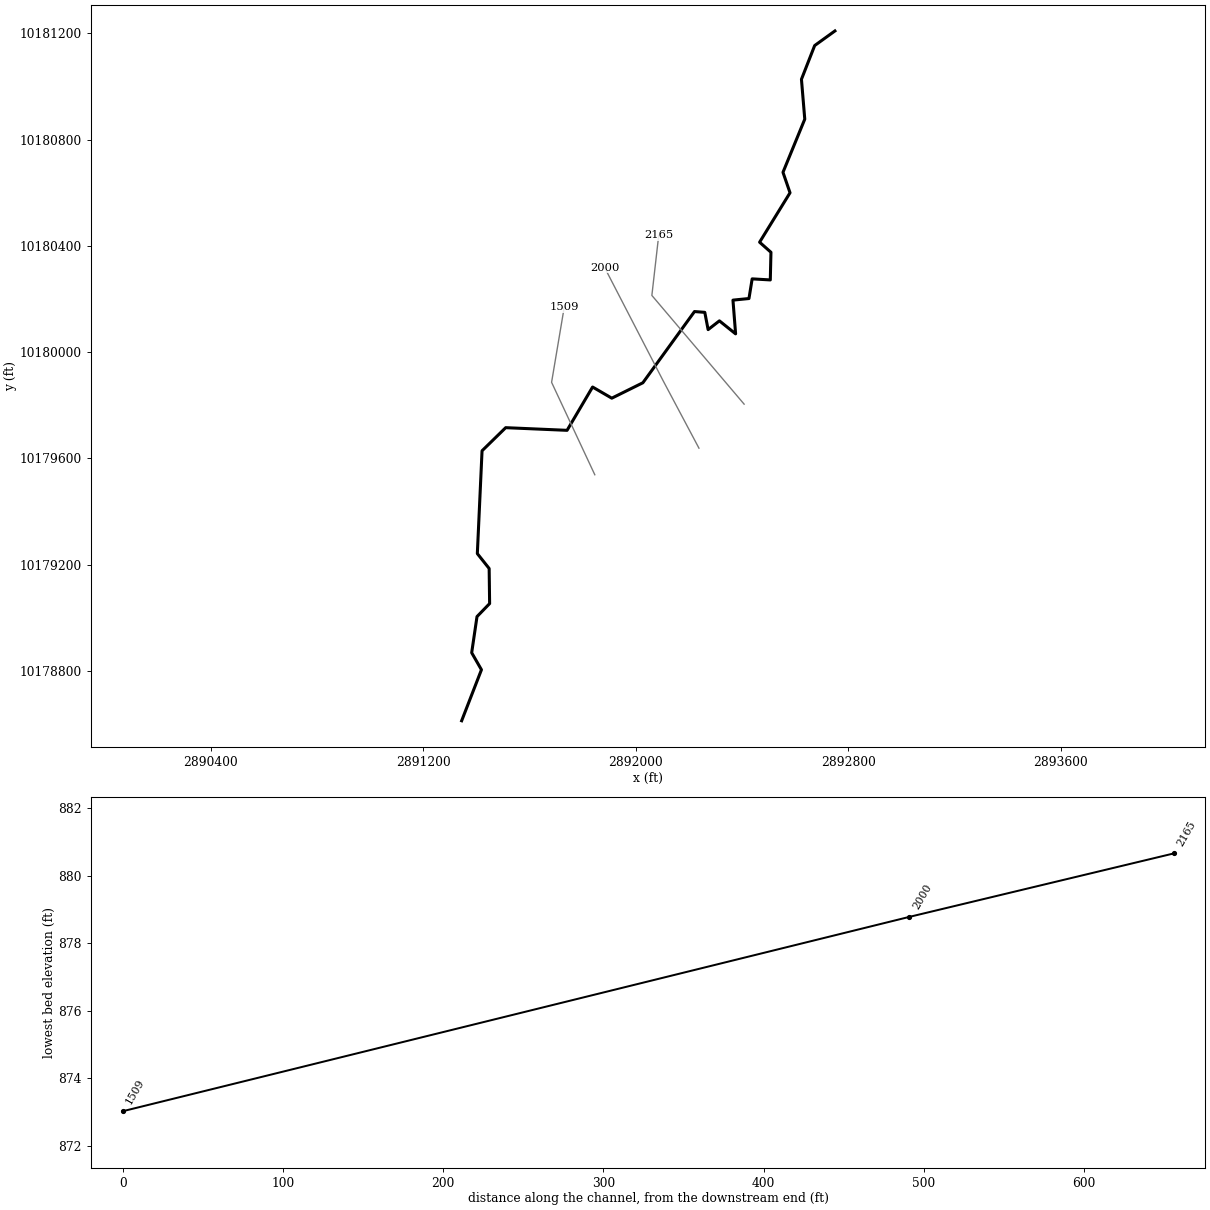
--- SANDY 38.prj (project) ---

Proj Title=SANDY 38 Base Level Engineering
Current Plan=p01
Default Exp/Contr=0.3,0.1
English Units
Geom File=g01
Flow File=f01
Plan File=p01
Y Axis Title=Elevation
X Axis Title(PF)=Main Channel Distance
X Axis Title(XS)=Station
BEGIN DESCRIPTION:
SANDY 38
END DESCRIPTION:
DSS Export Rating Curves= 0
DSS Export Rating Curve Sorted= 0
DSS Export Volume Flow Curves= 0
DXF OffsetX= 0
DXF OffsetY= 0
DXF ScaleX= 1
DXF ScaleY= 10

--- SANDY 38.p01 (plan) ---

Plan Title=Multiple Run
Short Identifier=Multiple
Geom File=g01
Flow File=f01
Subcritical Flow
K Sum by GR= 0
Std Step Tol= 0.01
Critical Tol= 0.01
Num of Std Step Trials= 20
Max Error Tol= 0.3
Flow Tol Ratio= 0.001
Split Flow NTrial= 30
Split Flow Tol= 0.02
Split Flow Ratio= 0.02
Log Output Level= 0
Friction Slope Method= 1
Unsteady Friction Slope Method= 2
Unsteady Bridges Friction Slope Method= 1
Parabolic Critical Depth
Global Vel Dist=  1 , 1 , 1
Global Log Level= 0
CheckData=True
Encroach Param= -1, 0, 0, 0
BEGIN DESCRIPTION:
Multiple Run
END DESCRIPTION:

--- SANDY 38.f01 (steady flow) ---

Flow Title=Multiple
Number of Profiles=7
Profile Names=10-year,25-year,50-year,1pct_min,100-year,1pct_plu,500-year
River Rch & RM= SANDY 38,Reach-1,2165
      22      28      37      16      50     150     106
Boundary for River Rch & Prof#=SANDY 38,Reach-1,1
Up Type=0
Dn Type=3
Dn Slope=0.005
Boundary for River Rch & Prof#=SANDY 38,Reach-1,2
Up Type=0
Dn Type=3
Dn Slope=0.005
Boundary for River Rch & Prof#=SANDY 38,Reach-1,3
Up Type=0
Dn Type=3
Dn Slope=0.005
Boundary for River Rch & Prof#=SANDY 38,Reach-1,4
Up Type=0
Dn Type=3
Dn Slope=0.005
Boundary for River Rch & Prof#=SANDY 38,Reach-1,5
Up Type=0
Dn Type=3
Dn Slope=0.005
Boundary for River Rch & Prof#=SANDY 38,Reach-1,6
Up Type=0
Dn Type=3
Dn Slope=0.005
Boundary for River Rch & Prof#=SANDY 38,Reach-1,7
Up Type=0
Dn Type=3
Dn Slope=0.005

--- SANDY 38.g01 (geometry) ---

Geom Title=Existing Conditions
Program Version=4.10

River Reach=SANDY 38        ,Reach-1
Reach XY= 30
      2892749.25       10181209.        2892673.       10181154.
      2892623.25       10181027.      2892635.75       10180877.
      2892553.75       10180677.      2892580.25       10180600.
      2892465.75       10180414.       2892508.5       10180376.
        2892506.       10180272.      2892437.75       10180276.
      2892425.75       10180202.       2892365.5       10180196.
       2892375.5       10180069.       2892314.5       10180118.
        2892272.       10180085.       2892259.5       10180150.
      2892220.75       10180153.       2892026.5       10179885.
       2891909.5       10179827.      2891837.25       10179869.
      2891741.25       10179706.      2891510.25       10179716.
      2891421.25       10179629.       2891403.5       10179242.
        2891448.       10179186.      2891449.75       10179054.
      2891402.25       10179005.      2891382.25       10178869.
        2891419.       10178805.       2891344.5       10178613.

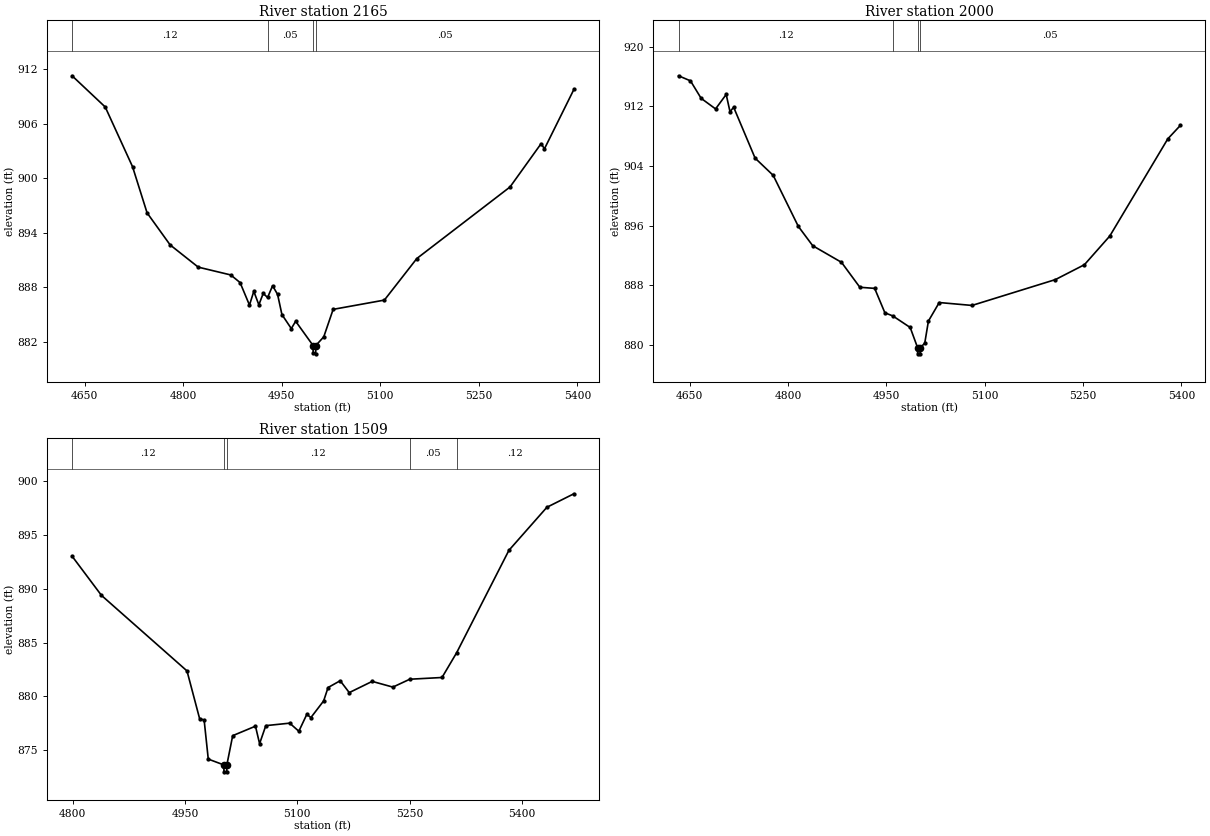
Type RM Length L Ch R = 1 ,2165    ,165,165,165
BEGIN DESCRIPTION:
SANDY 38 3.0
END DESCRIPTION:
XS GIS Cut Line= 3
       2892407.5     10179804.55      2892060.34     10180213.64
      2892086.09     10180439.64
#Sta/Elev= 30
  4630.7  911.29  4681.2  907.85  4722.8  901.27  4744.9  896.19    4780  892.66
  4822.8  890.21  4872.3  889.35  4886.5  888.51  4900.8  886.03  4907.4  887.54
  4915.1  886.06  4921.7  887.31  4928.4  886.87    4936  888.16  4943.6  887.21
  4950.2  884.99  4964.5  883.44  4971.1  884.25  4997.7  881.57 4997.75  880.72
 5001.67  880.66  5001.7  881.57  5013.9  882.53  5028.2  885.56  5106.2  886.58
  5155.6  891.16  5297.5  899.04  5344.9  903.82  5349.9  903.24  5394.7  909.78
#Mann= 4 ,-1 , 0
  4630.7     .12       0  4928.4     .05       0  4997.7     .05       0
  5001.7     .05       0
Bank Sta=4997.7,5001.7
XS Rating Curve= 0 ,0
Exp/Cntr=0.3,0.1

Type RM Length L Ch R = 1 ,2000    ,491,491,491
BEGIN DESCRIPTION:
SANDY 38 2.0
END DESCRIPTION:
XS GIS Cut Line= 3
      2892237.53     10179638.87      2892102.81     10179892.43
      2891883.15     10180317.39
#Sta/Elev= 30
  4632.9  916.12  4651.1  915.44  4667.4  913.09  4689.4  911.67  4705.6  913.61
  4711.4   911.3    4717  911.89  4749.7  905.06  4777.3  902.75  4815.6   895.9
  4837.6   893.3  4881.5  891.07  4909.5  887.72  4932.1  887.57  4947.7  884.29
  4959.8  883.87  4986.3  882.32  4997.6   879.6 4997.65  878.78 5001.57  878.82
  5001.6   879.6  5008.5  880.21  5014.1  883.18  5030.6  885.67  5080.6  885.28
  5207.8  888.75  5252.1  890.75  5290.8   894.6  5379.3  907.65  5398.4  909.45
#Mann= 4 ,-1 , 0
  4632.9     .12       0  4959.8     .05       0  4997.6     .05       0
  5001.6     .05       0
Bank Sta=4997.6,5001.6
XS Rating Curve= 0 ,0
Exp/Cntr=0.3,0.1

Type RM Length L Ch R = 1 ,1509    ,0,0,0
BEGIN DESCRIPTION:
SANDY 38 1.0
END DESCRIPTION:
XS GIS Cut Line= 3
      2891845.54     10179538.89      2891682.94     10179886.66
      2891730.41     10180168.59
#Sta/Elev= 30
  4799.3     893  4838.5  889.37  4952.7  882.37  4969.5  877.96  4975.6  877.81
  4981.1   874.2  5001.9  873.66 5002.03  873.05 5005.83  873.02  5005.9  873.66
  5013.7  876.37  5044.1  877.25  5049.6  875.63  5057.9   877.3  5089.8  877.53
    5102  876.78  5112.6  878.34  5118.1  878.05  5135.1  879.59    5141  880.83
  5157.2  881.46  5169.3  880.36  5199.9   881.4  5227.5  880.87  5250.1   881.6
  5293.1  881.76  5312.6  884.05  5382.4  893.54  5433.1  897.53  5469.1  898.78
#Mann= 5 ,-1 , 0
  4799.3     .12       0  5001.9     .05       0  5005.9     .12       0
  5250.1     .05       0  5312.6     .12       0
Bank Sta=5001.9,5005.9
XS Rating Curve= 0 ,0
Exp/Cntr=0.3,0.1

Chan Stop Cuts=-1
Use User Specified Reach Order=0
Composite Channel Slope=5