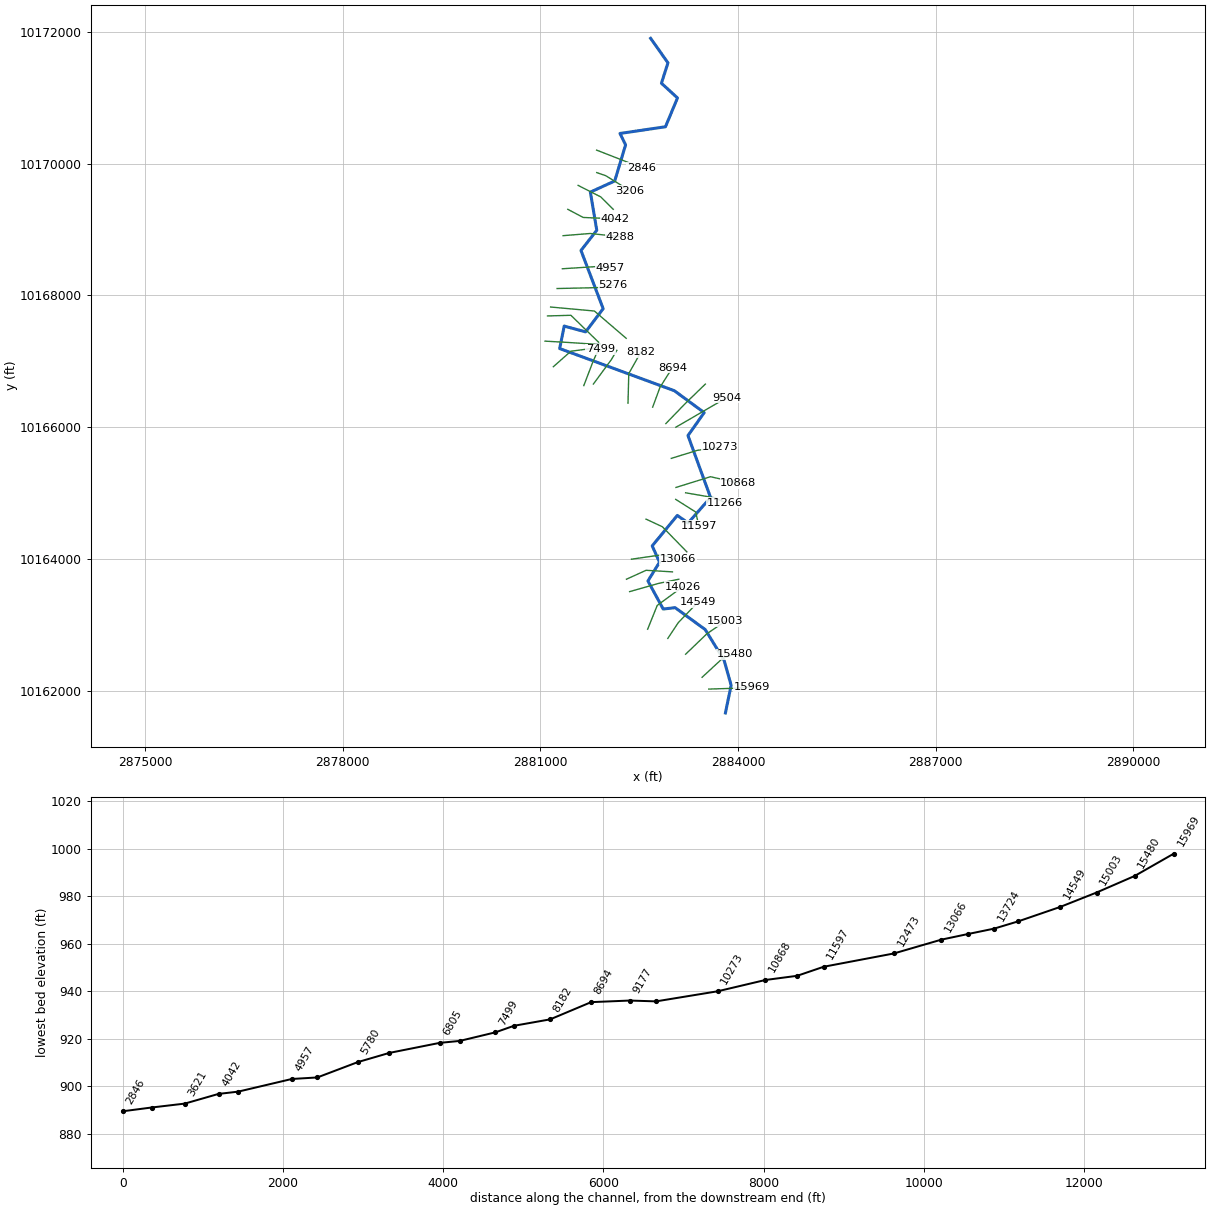
--- SHIP HOLLOW CREEK.prj (project) ---

Proj Title=SHIP HOLLOW CREEK Base Level Engineering
Current Plan=p01
Default Exp/Contr=0.3,0.1
English Units
Geom File=g01
Flow File=f01
Plan File=p01
BEGIN DESCRIPTION:
SHIP HOLLOW CREEK
END DESCRIPTION:

--- SHIP HOLLOW CREEK.p01 (plan) ---

Plan Title=Multiple Run
Short Identifier=Multiple
Geom File=g01
Flow File=f01
Subcritical Flow
K Sum by GR= 0
Std Step Tol= 0.01
Critical Tol= 0.01
Num of Std Step Trials= 20
Max Error Tol= 0.3
Flow Tol Ratio= 0.001
Split Flow NTrial= 30
Split Flow Tol= 0.02
Split Flow Ratio= 0.02
Log Output Level= 0
Friction Slope Method= 1
Unsteady Friction Slope Method= 2
Unsteady Bridges Friction Slope Method= 1
Parabolic Critical Depth
Global Vel Dist=  1 , 1 , 1
Global Log Level= 0
CheckData=True
Encroach Param= -1, 0, 0, 0
BEGIN DESCRIPTION:
Multiple Run
END DESCRIPTION:

--- SHIP HOLLOW CREEK.f01 (steady flow) ---

Flow Title=Multiple
Number of Profiles=7
Profile Names=10-year,25-year,50-year,1pct_min,100-year,1pct_plu,500-year
River Rch & RM= SHIP HOLLOW CREE,Reach-1,15969
      65     125     195     101     306     924     806
River Rch & RM= SHIP HOLLOW CREE,Reach-1,2372
      77     153     243     127     384    1161    1029
Boundary for River Rch & Prof#=SHIP HOLLOW CREE,Reach-1,1
Up Type=0
Dn Type=3
Dn Slope=0.005
Boundary for River Rch & Prof#=SHIP HOLLOW CREE,Reach-1,2
Up Type=0
Dn Type=3
Dn Slope=0.005
Boundary for River Rch & Prof#=SHIP HOLLOW CREE,Reach-1,3
Up Type=0
Dn Type=3
Dn Slope=0.005
Boundary for River Rch & Prof#=SHIP HOLLOW CREE,Reach-1,4
Up Type=0
Dn Type=3
Dn Slope=0.005
Boundary for River Rch & Prof#=SHIP HOLLOW CREE,Reach-1,5
Up Type=0
Dn Type=3
Dn Slope=0.005
Boundary for River Rch & Prof#=SHIP HOLLOW CREE,Reach-1,6
Up Type=0
Dn Type=3
Dn Slope=0.005
Boundary for River Rch & Prof#=SHIP HOLLOW CREE,Reach-1,7
Up Type=0
Dn Type=3
Dn Slope=0.005

--- SHIP HOLLOW CREEK.g01 (geometry) ---

Geom Title=Existing Conditions

River Reach=SHIP HOLLOW CREE,Reach-1
Reach XY= 30
      2883810.00     10161662.00      2883896.75     10162082.00
      2883790.00     10162461.00      2883503.50     10162927.00
      2883046.50     10163260.00      2882865.50     10163239.00
      2882633.75     10163665.00      2882809.50     10163949.00
      2882698.75     10164198.00      2883080.25     10164660.00
      2883243.00     10164544.00      2883584.25     10164932.00
      2883241.75     10165871.00      2883487.75     10166220.00
      2883034.75     10166552.00      2881294.00     10167192.00
      2881362.75     10167533.00      2881687.75     10167445.00
      2881954.00     10167797.00      2881617.50     10168680.00
      2881857.00     10168987.00      2881760.00     10169566.00
      2882129.50     10169735.00      2882294.50     10170283.00
      2882209.50     10170456.00      2882900.25     10170558.00
      2883082.50     10170995.00      2882838.75     10171218.00
      2882937.50     10171528.00      2882674.75     10171900.00

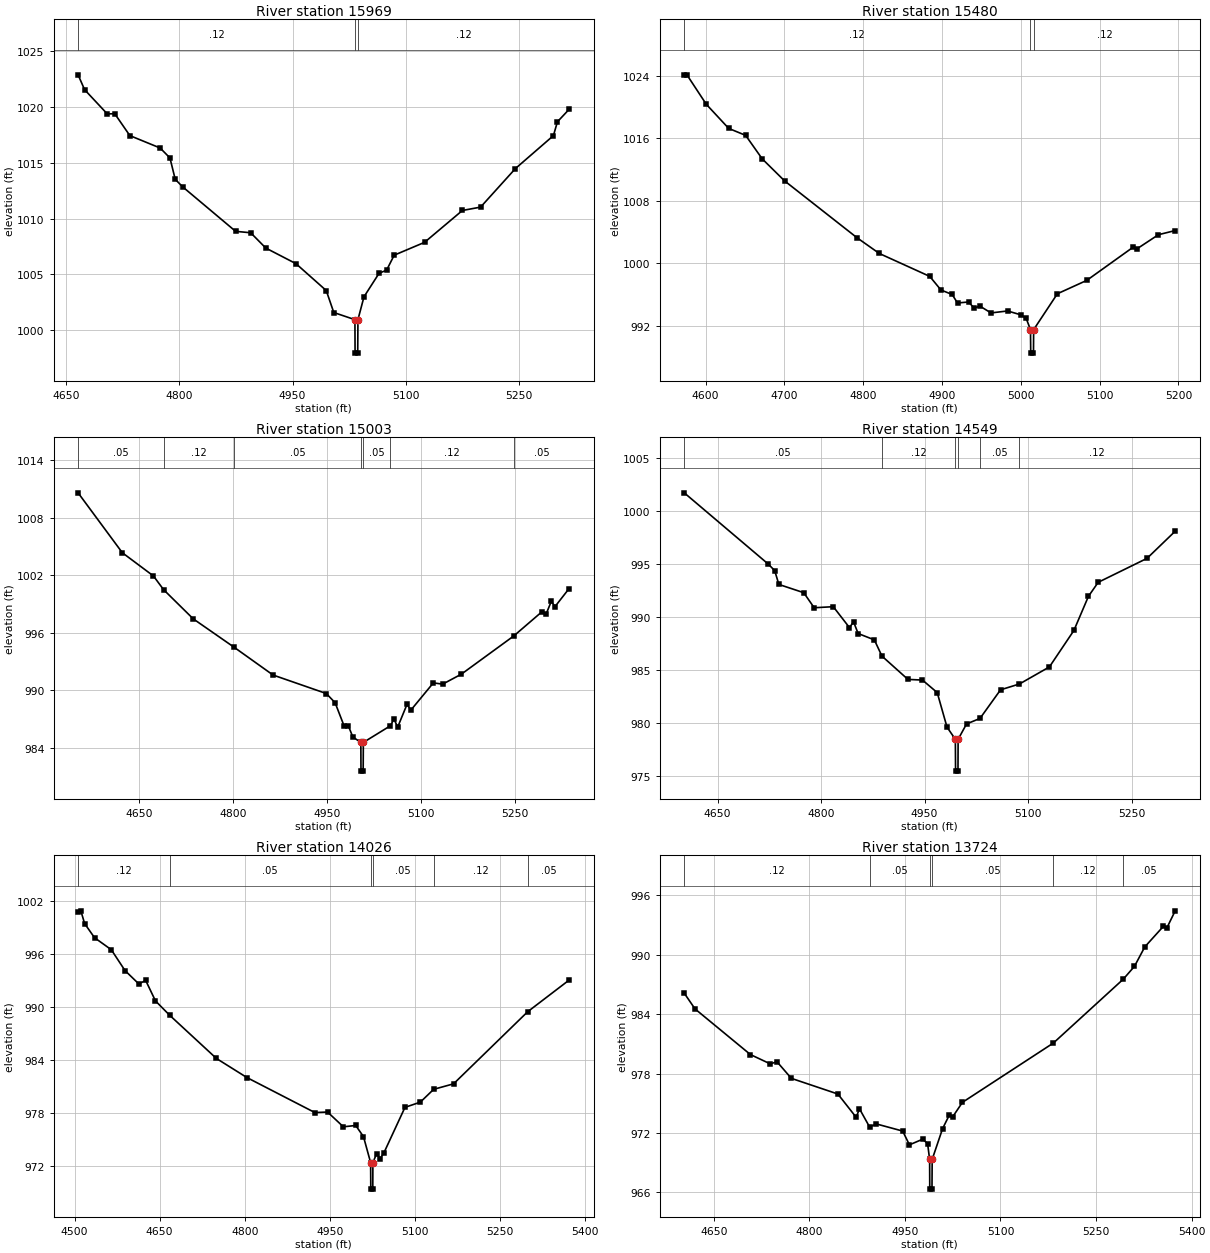
Type RM Length L Ch R = 1,15969,489,489,489
BEGIN DESCRIPTION:
SHIP HOLLOW CREEK 31.0
END DESCRIPTION:
XS GIS Cut Line= 3
      2883557.09     10162024.27      2883984.70     10162038.00
      2884206.32     10162059.57
#Sta/Elev= 30
  4665.8 1022.90  4674.4 1021.57  4704.4 1019.40  4714.4 1019.41  4734.4 1017.45
  4774.5 1016.34  4787.5 1015.45  4794.5 1013.53  4804.5 1012.85  4874.5 1008.87
  4894.5 1008.74  4914.5 1007.37  4954.5 1005.97  4994.6 1003.56  5004.6 1001.59
  5032.6 1000.95  5032.8  997.95  5036.3  997.95  5036.6 1000.95  5044.6 1003.00
  5064.6 1005.11  5074.6 1005.39  5084.6 1006.73  5124.8 1007.88  5175.0 1010.74
  5199.1 1011.04  5245.3 1014.50  5295.6 1017.45  5300.9 1018.69  5316.3 1019.80
#Mann=3,-1,0
  4665.8    0.12       0  5032.6    0.07       0  5036.6    0.12       0
Bank Sta=5032.6,5036.6
Exp/Cntr=0.3,0.1

Type RM Length L Ch R = 1,15480,477,477,477
BEGIN DESCRIPTION:
SHIP HOLLOW CREEK 30.0
END DESCRIPTION:
XS GIS Cut Line= 3
      2883455.71     10162203.14      2883769.25     10162493.00
      2883955.70     10162553.12
#Sta/Elev= 30
  4573.0 1024.12  4576.4 1024.12  4601.0 1020.35  4629.4 1017.27  4650.9 1016.38
  4671.9 1013.38  4700.3 1010.56  4792.1 1003.30  4820.5 1001.28  4884.5  998.35
  4898.7  996.61  4912.9  996.04  4919.7  994.95  4933.9  995.08  4940.7  994.29
  4948.0  994.56  4962.2  993.68  4983.2  993.93  5000.0  993.44  5006.8  992.99
  5012.3  991.54  5012.6  988.54  5016.1  988.54  5016.3  991.54  5046.4  996.13
  5083.7  997.84  5142.6 1002.09  5147.8 1001.90  5174.6 1003.68  5195.9 1004.21
#Mann=3,-1,0
  4573.0    0.12       0  5012.3    0.07       0  5016.3    0.12       0
Bank Sta=5012.3,5016.3
Exp/Cntr=0.3,0.1

Type RM Length L Ch R = 1,15003,454,454,454
BEGIN DESCRIPTION:
SHIP HOLLOW CREEK 29.0
END DESCRIPTION:
XS GIS Cut Line= 3
      2883205.69     10162553.11      2883528.25     10162863.00
      2883805.67     10163053.10
#Sta/Elev= 30
  4552.7 1010.62  4623.3 1004.36  4673.0 1001.93  4689.2 1000.50  4736.5  997.45
  4801.6  994.49  4863.9  991.58  4948.8  989.65  4962.9  988.69  4977.1  986.29
  4984.0  986.28  4991.2  985.11  5004.0  984.54  5004.2  981.54  5007.7  981.54
  5008.0  984.54  5051.2  986.28  5056.8  986.98  5062.8  986.14  5077.7  988.52
  5083.8  987.91  5119.7  990.76  5134.6  990.63  5164.4  991.67  5248.0  995.66
  5293.0  998.19  5300.0  998.00  5307.9  999.27  5314.0  998.74  5336.3 1000.61
#Mann=7,-1,0
  4552.7    0.05       0  4689.2    0.12       0  4801.6    0.05       0
  5004.0    0.05       0  5008.0    0.05       0  5051.2    0.12       0
  5248.0    0.05       0
Bank Sta=5004,5008
Exp/Cntr=0.3,0.1

Type RM Length L Ch R = 1,14549,523,523,523
BEGIN DESCRIPTION:
SHIP HOLLOW CREEK 28.0
END DESCRIPTION:
XS GIS Cut Line= 3
      2882935.32     10162793.14      2883094.21     10163032.45
      2883388.26     10163338.26
#Sta/Elev= 30
  4601.7 1001.72  4723.8  994.98  4732.8  994.38  4738.8  993.08  4774.9  992.30
  4790.0  990.88  4817.7  990.98  4841.1  989.01  4847.1  989.55  4853.7  988.45
  4877.2  987.85  4888.2  986.32  4925.9  984.12  4946.9  984.06  4968.3  982.88
  4982.5  979.62  4994.6  978.47  4994.9  975.47  4998.4  975.47  4998.6  978.47
  5010.8  979.92  5030.3  980.44  5060.1  983.14  5087.5  983.69  5130.9  985.30
  5166.4  988.74  5187.5  991.96  5201.6  993.28  5272.4  995.54  5313.2  998.10
#Mann=6,-1,0
  4601.7    0.05       0  4888.2    0.12       0  4994.6    0.07       0
  4998.6    0.12       0  5030.3    0.05       0  5087.5    0.12       0
Bank Sta=4994.6,4998.6
Exp/Cntr=0.3,0.1

Type RM Length L Ch R = 1,14026,302,302,302
BEGIN DESCRIPTION:
SHIP HOLLOW CREEK 27.0
END DESCRIPTION:
XS GIS Cut Line= 3
      2882629.35     10162932.42      2882774.49     10163293.32
      2883158.91     10163575.75
#Sta/Elev= 30
  4506.1 1000.76  4511.0 1000.89  4517.6  999.45  4535.1  997.85  4564.7  996.49
  4588.9  994.13  4613.1  992.63  4625.4  993.01  4642.6  990.70  4667.6  989.08
  4750.1  984.19  4803.9  982.03  4923.8  978.07  4946.2  978.13  4974.0  976.46
  4995.8  976.61  5009.5  975.35  5022.1  972.41  5022.4  969.41  5025.9  969.41
  5026.1  972.41  5032.6  973.41  5038.8  972.86  5045.5  973.51  5082.7  978.66
  5109.8  979.25  5133.3  980.70  5168.4  981.32  5299.2  989.48  5372.1  993.05
#Mann=6,-1,0
  4506.1    0.12       0  4667.6    0.05       0  5022.1    0.05       0
  5026.1    0.05       0  5133.3    0.12       0  5299.2    0.05       0
Bank Sta=5022.1,5026.1
Exp/Cntr=0.3,0.1

Type RM Length L Ch R = 1,13724,330,330,330
BEGIN DESCRIPTION:
SHIP HOLLOW CREEK 26.0
END DESCRIPTION:
XS GIS Cut Line= 3
      2882355.69     10163503.11      2882798.03     10163628.72
      2883102.37     10163691.15
#Sta/Elev= 30
  4603.7  986.12  4620.6  984.53  4707.6  979.92  4738.8  978.98  4749.2  979.20
  4771.8  977.52  4844.8  975.94  4873.5  973.59  4878.7  974.45  4894.6  972.61
  4905.2  972.92  4946.5  972.20  4957.1  970.81  4977.9  971.38  4985.6  970.94
  4988.8  969.34  4989.0  966.34  4992.5  966.34  4992.8  969.34  5009.1  972.44
  5019.5  973.79  5024.7  973.61  5040.3  975.10  5183.1  981.09  5292.7  987.53
  5310.3  988.83  5326.5  990.79  5355.6  992.86  5360.7  992.65  5374.2  994.43
#Mann=6,-1,0
  4603.7    0.12       0  4894.6    0.05       0  4988.8    0.05       0
  4992.8    0.05       0  5183.1    0.12       0  5292.7    0.05       0
Bank Sta=4988.8,4992.8
Exp/Cntr=0.3,0.1

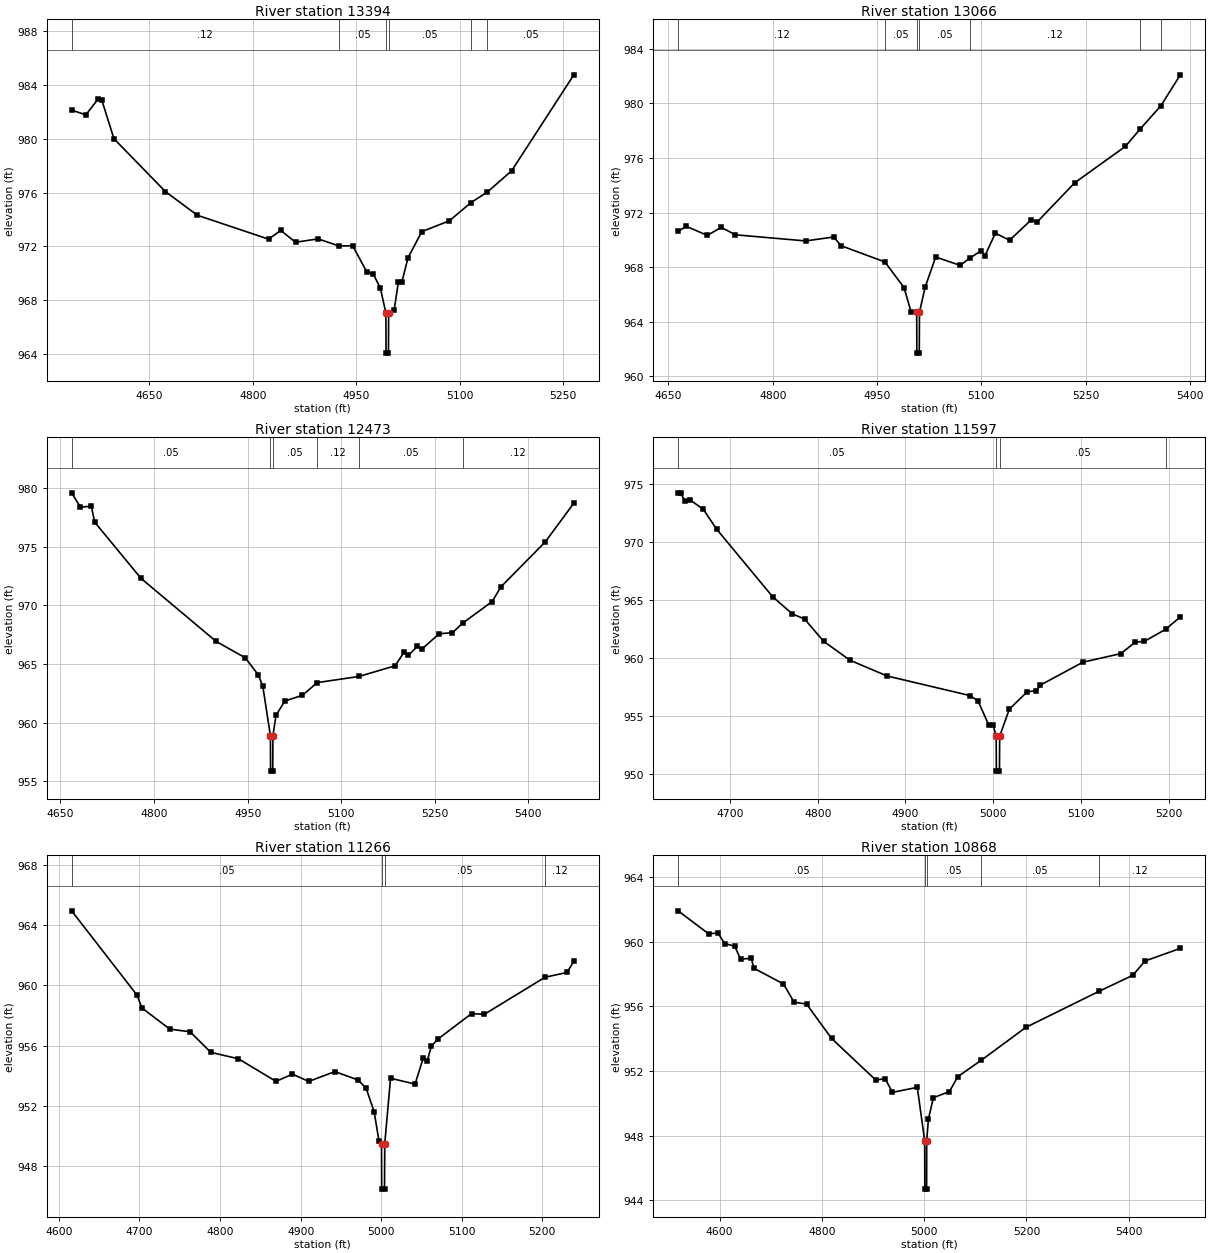
Type RM Length L Ch R = 1,13394,328,328,328
BEGIN DESCRIPTION:
SHIP HOLLOW CREEK 25.0
END DESCRIPTION:
XS GIS Cut Line= 3
      2882307.68     10163691.50      2882605.81     10163826.83
      2883005.70     10163803.11
#Sta/Elev= 30
  4537.3  982.14  4557.9  981.79  4575.5  982.96  4581.0  982.89  4598.6  980.01
  4673.3  976.07  4719.5  974.31  4822.8  972.53  4840.4  973.18  4861.9  972.30
  4894.6  972.55  4925.0  972.02  4944.7  972.04  4964.8  970.12  4974.8  969.90
  4984.8  968.89  4992.8  967.04  4993.1  964.04  4996.6  964.04  4996.8  967.04
  5004.8  967.25  5010.9  969.31  5015.9  969.32  5024.9  971.14  5044.9  973.09
  5085.0  973.90  5116.1  975.25  5139.7  976.03  5175.1  977.62  5265.3  984.77
#Mann=6,-1,0
  4537.3    0.12       0  4925.0    0.05       0  4992.8    0.05       0
  4996.8    0.05       0  5116.1    0.12       0  5139.7    0.05       0
Bank Sta=4992.8,4996.8
Exp/Cntr=0.3,0.1

Type RM Length L Ch R = 1,13066,593,593,593
BEGIN DESCRIPTION:
Mapping XS 18e9191d
END DESCRIPTION:
XS GIS Cut Line= 3
      2882384.19     10163995.52      2882849.03     10164062.20
      2883091.42     10163991.83
#Sta/Elev= 30
  4664.0  970.62  4675.6  970.99  4705.9  970.33  4726.1  970.91  4746.3  970.37
  4847.4  969.92  4887.8  970.21  4898.2  969.57  4961.3  968.38  4988.8  966.50
  4998.9  964.73  5007.0  964.70  5007.2  961.70  5010.7  961.70  5011.0  964.70
  5019.1  966.53  5034.3  968.74  5069.6  968.13  5083.3  968.66  5099.8  969.21
  5104.9  968.81  5120.1  970.49  5140.5  969.97  5171.8  971.47  5180.6  971.33
  5234.2  974.18  5307.1  976.85  5327.8  978.09  5358.2  979.83  5386.0  982.09
#Mann=7,-1,0
  4664.0    0.12       0  4961.3    0.05       0  5007.0    0.05       0
  5011.0    0.05       0  5083.3    0.12       0  5327.8    0.05       0
  5358.2    0.12       0
Bank Sta=5007,5011
Exp/Cntr=0.3,0.1

Type RM Length L Ch R = 1,12473,876,876,876
BEGIN DESCRIPTION:
SHIP HOLLOW CREEK 24.0
END DESCRIPTION:
XS GIS Cut Line= 3
      2882605.73     10164603.09      2882852.95     10164487.83
      2883224.31     10164106.70
#Sta/Elev= 30
  4667.9  979.58  4682.0  978.36  4699.4  978.44  4704.9  977.08  4779.0  972.30
  4899.6  966.92  4946.2  965.53  4967.1  964.07  4974.3  963.11  4986.5  958.88
  4986.7  955.88  4990.2  955.88  4990.5  958.88  4995.4  960.63  5009.6  961.85
  5037.9  962.34  5061.5  963.42  5128.3  963.94  5186.3  964.85  5200.5  965.99
  5207.6  965.73  5221.8  966.50  5228.7  966.25  5257.0  967.58  5278.3  967.67
  5294.8  968.49  5341.9  970.32  5356.1  971.58  5426.8  975.39  5472.8  978.70
#Mann=6,-1,0
  4667.9    0.05       0  4986.5    0.05       0  4990.5    0.05       0
  5061.5    0.12       0  5128.3    0.05       0  5294.8    0.12       0
Bank Sta=4986.5,4990.5
Exp/Cntr=0.3,0.1

Type RM Length L Ch R = 1,11597,331,331,331
BEGIN DESCRIPTION:
SHIP HOLLOW CREEK 23.0
END DESCRIPTION:
XS GIS Cut Line= 3
      2883055.72     10164903.09      2883359.00     10164711.00
      2883405.69     10164503.08
#Sta/Elev= 30
  4641.0  974.24  4643.9  974.24  4648.6  973.52  4654.5  973.64  4669.8  972.81
  4685.0  971.10  4748.6  965.30  4771.2  963.81  4785.0  963.38  4806.7  961.46
  4836.7  959.83  4879.1  958.47  4973.2  956.79  4982.5  956.34  4995.1  954.22
  5000.0  954.22  5003.3  953.28  5003.6  950.28  5007.1  950.28  5007.3  953.28
  5018.3  955.61  5038.8  957.12  5048.6  957.19  5053.8  957.69  5102.2  959.66
  5145.5  960.40  5161.8  961.39  5172.1  961.45  5196.4  962.49  5213.1  963.56
#Mann=4,-1,0
  4641.0    0.05       0  5003.3    0.05       0  5007.3    0.05       0
  5196.4    0.12       0
Bank Sta=5003.3,5007.3
Exp/Cntr=0.3,0.1

Type RM Length L Ch R = 1,11266,398,398,398
BEGIN DESCRIPTION:
SHIP HOLLOW CREEK 22.0
END DESCRIPTION:
XS GIS Cut Line= 3
      2883205.64     10165003.12      2883657.14     10164925.23
      2883805.69     10164853.11
#Sta/Elev= 30
  4615.8  964.94  4697.0  959.34  4703.1  958.49  4737.6  957.09  4762.9  956.91
  4788.4  955.55  4822.8  955.12  4869.5  953.62  4889.8  954.10  4910.1  953.62
  4942.5  954.27  4971.0  953.72  4981.2  953.18  4991.3  951.59  4997.3  949.64
  5000.4  949.47  5000.6  946.47  5004.1  946.47  5004.4  949.47  5011.6  953.83
  5042.0  953.44  5052.1  955.15  5057.2  954.98  5062.3  955.97  5070.7  956.44
  5112.2  958.12  5127.9  958.07  5203.3  960.53  5230.6  960.85  5239.1  961.59
#Mann=4,-1,0
  4615.8    0.05       0  5000.4    0.05       0  5004.4    0.05       0
  5203.3    0.12       0
Bank Sta=5000.4,5004.4
Exp/Cntr=0.3,0.1

Type RM Length L Ch R = 1,10868,595,595,595
BEGIN DESCRIPTION:
SHIP HOLLOW CREEK 21.0
END DESCRIPTION:
XS GIS Cut Line= 3
      2883058.90     10165084.11      2883582.60     10165246.91
      2884006.25     10165152.77
#Sta/Elev= 30
  4518.7  961.90  4578.2  960.48  4596.7  960.53  4609.6  959.88  4629.3  959.71
  4641.0  958.92  4661.8  958.96  4667.0  958.35  4724.8  957.38  4745.7  956.25
  4769.9  956.14  4819.0  954.01  4905.4  951.44  4923.7  951.53  4937.9  950.68
  4986.6  950.99  5001.0  947.70  5001.3  944.70  5004.8  944.70  5005.0  947.70
  5008.3  949.02  5018.0  950.35  5049.4  950.73  5066.1  951.66  5111.6  952.66
  5199.1  954.70  5342.4  956.93  5408.3  957.92  5432.1  958.80  5501.1  959.58
#Mann=5,-1,0
  4518.7    0.05       0  5001.0    0.05       0  5005.0    0.05       0
  5111.6    0.05       0  5342.4    0.12       0
Bank Sta=5001,5005
Exp/Cntr=0.3,0.1

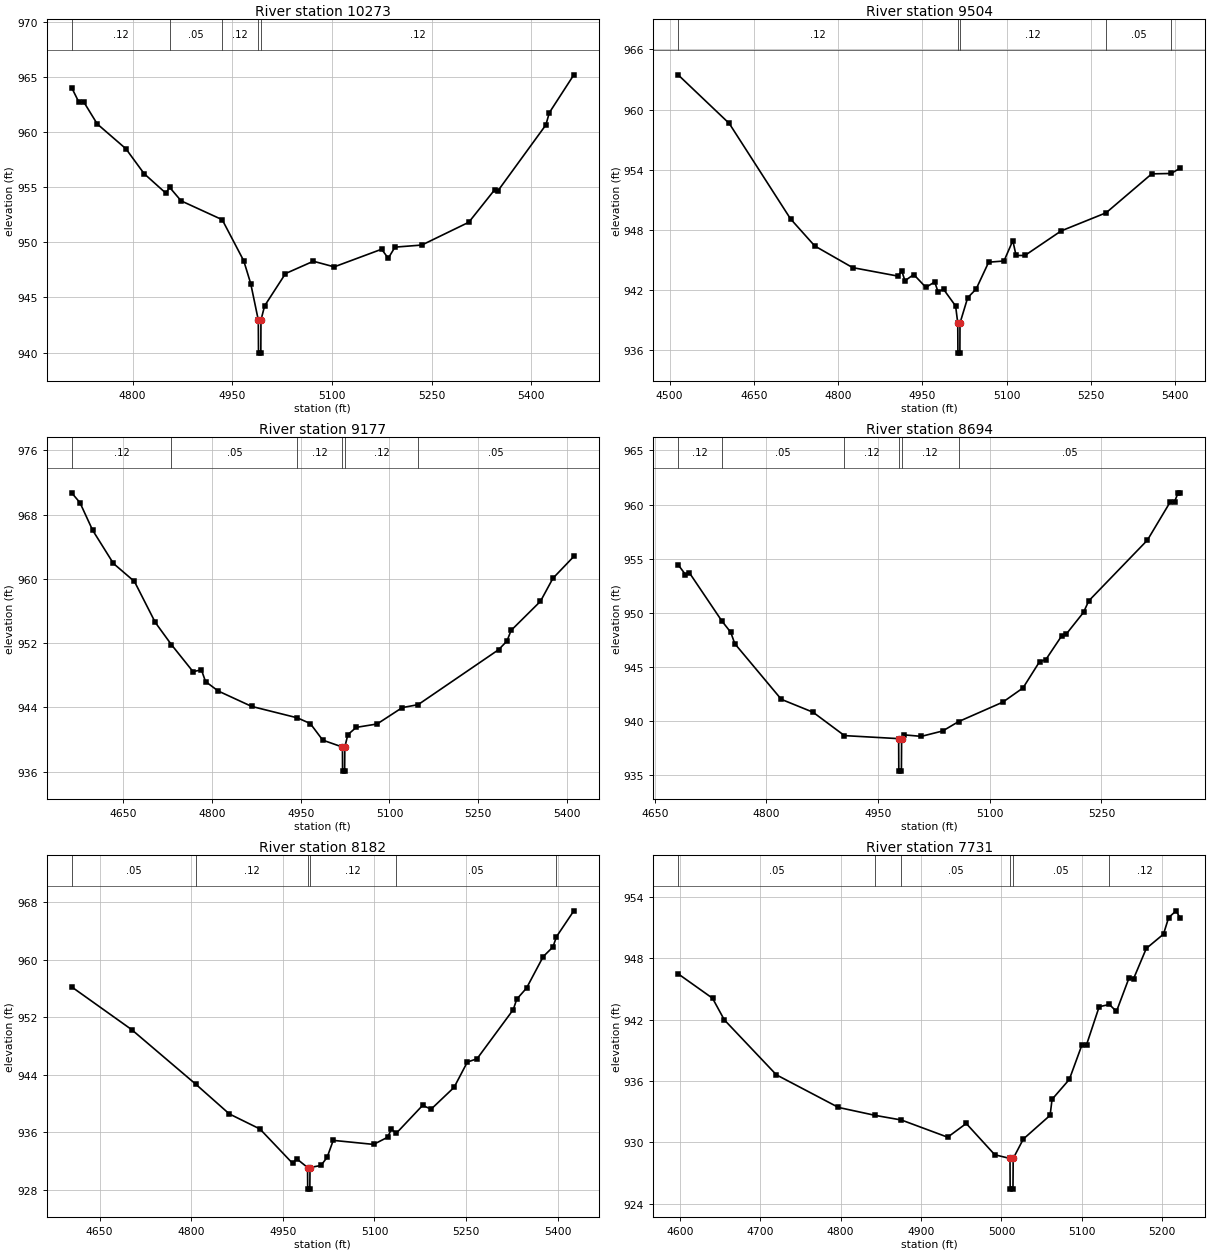
Type RM Length L Ch R = 1,10273,769,769,769
BEGIN DESCRIPTION:
SHIP HOLLOW CREEK 20.0
END DESCRIPTION:
XS GIS Cut Line= 3
      2882988.27     10165525.43      2883382.54     10165647.04
      2883722.22     10165693.90
#Sta/Elev= 30
  4708.3  964.05  4719.4  962.70  4726.5  962.75  4746.8  960.75  4789.9  958.50
  4817.3  956.24  4850.0  954.47  4855.8  954.99  4873.0  953.77  4934.8  952.06
  4967.2  948.33  4977.7  946.26  4989.1  942.95  4989.4  939.95  4992.9  939.95
  4993.1  942.95  4998.6  944.24  5030.0  947.17  5071.9  948.29  5103.3  947.78
  5174.6  949.38  5184.6  948.56  5194.7  949.57  5235.1  949.76  5305.8  951.83
  5344.7  954.78  5349.7  954.69  5421.7  960.66  5426.9  961.77  5463.8  965.21
#Mann=5,-1,0
  4708.3    0.12       0  4855.8    0.05       0  4934.8    0.12       0
  4989.1    0.07       0  4993.1    0.12       0
Bank Sta=4989.1,4993.1
Exp/Cntr=0.3,0.1

Type RM Length L Ch R = 1,9504,327,327,327
BEGIN DESCRIPTION:
SHIP HOLLOW CREEK 19.0
END DESCRIPTION:
XS GIS Cut Line= 3
      2883056.96     10165998.15      2883280.54     10166127.59
      2883829.72     10166447.29
#Sta/Elev= 30
  4515.2  963.46  4606.2  958.61  4715.3  949.09  4758.4  946.39  4825.8  944.23
  4906.8  943.38  4913.1  943.93  4918.9  942.92  4934.6  943.54  4956.2  942.26
  4971.9  942.80  4977.7  941.83  4987.6  942.07  5009.1  940.40  5012.9  938.70
  5013.2  935.70  5016.7  935.70  5016.9  938.70  5030.6  941.23  5045.6  942.09
  5067.9  944.77  5095.2  944.89  5110.9  946.92  5116.7  945.44  5132.4  945.44
  5196.9  947.89  5277.0  949.70  5358.1  953.58  5392.7  953.62  5409.0  954.16
#Mann=5,-1,0
  4515.2    0.12       0  5012.9    0.07       0  5016.9    0.12       0
  5277.0    0.05       0  5392.7    0.12       0
Bank Sta=5012.9,5016.9
Exp/Cntr=0.3,0.1

Type RM Length L Ch R = 1,9177,483,483,483
BEGIN DESCRIPTION:
SHIP HOLLOW CREEK 18.0
END DESCRIPTION:
XS GIS Cut Line= 3
      2882905.69     10166053.12      2883209.75     10166367.00
      2883505.66     10166653.09
#Sta/Elev= 30
  4563.0  970.71  4577.0  969.49  4598.4  966.06  4633.6  961.91  4669.1  959.67
  4704.3  954.57  4731.6  951.80  4768.1  948.44  4782.3  948.66  4789.2  947.21
  4810.6  946.03  4867.2  944.11  4944.2  942.69  4966.2  941.98  4987.3  939.91
  5020.6  939.05  5020.8  936.05  5024.3  936.05  5024.6  939.05  5029.7  940.59
  5043.9  941.50  5079.1  941.92  5121.6  943.96  5148.5  944.33  5284.4  951.17
  5298.6  952.25  5305.5  953.57  5355.2  957.20  5376.3  960.07  5411.6  962.79
#Mann=6,-1,0
  4563.0    0.12       0  4731.6    0.05       0  4944.2    0.12       0
  5020.6    0.07       0  5024.6    0.12       0  5148.5    0.05       0
Bank Sta=5020.6,5024.6
Exp/Cntr=0.3,0.1

Type RM Length L Ch R = 1,8694,512,512,512
BEGIN DESCRIPTION:
SHIP HOLLOW CREEK 17.0
END DESCRIPTION:
XS GIS Cut Line= 3
      2882705.68     10166303.11      2882816.00     10166602.00
      2883005.70     10166903.13
#Sta/Elev= 30
  4681.4  954.44  4691.3  953.53  4696.6  953.69  4740.0  949.26  4752.1  948.20
  4757.5  947.15  4820.0  942.01  4862.6  940.82  4904.8  938.66  4977.6  938.38
  4977.8  935.38  4981.3  935.38  4981.6  938.38  4984.9  938.73  5008.0  938.59
  5036.8  939.09  5058.0  939.95  5117.5  941.75  5144.6  943.06  5166.8  945.48
  5175.2  945.67  5196.4  947.85  5202.3  948.00  5225.9  950.04  5232.9  951.10
  5311.7  956.71  5342.3  960.23  5348.2  960.26  5352.9  961.08  5355.9  961.08
#Mann=6,-1,0
  4681.4    0.12       0  4740.0    0.05       0  4904.8    0.12       0
  4977.6    0.07       0  4981.6    0.12       0  5058.0    0.05       0
Bank Sta=4977.6,4981.6
Exp/Cntr=0.3,0.1

Type RM Length L Ch R = 1,8182,451,451,451
BEGIN DESCRIPTION:
SHIP HOLLOW CREEK 16.0
END DESCRIPTION:
XS GIS Cut Line= 3
      2882331.21     10166364.96      2882342.98     10166812.14
      2882526.90     10167138.90
#Sta/Elev= 30
  4604.2  956.20  4702.4  950.27  4807.0  942.72  4862.4  938.56  4912.5  936.47
  4966.0  931.70  4972.5  932.35  4990.5  931.12  4990.7  928.12  4994.2  928.12
  4994.5  931.12  5012.5  931.41  5022.5  932.53  5032.5  934.89  5098.6  934.33
  5121.5  935.32  5127.8  936.45  5135.6  935.86  5178.9  939.75  5192.8  939.22
  5230.4  942.25  5252.1  945.76  5268.0  946.22  5327.3  953.04  5333.0  954.49
  5349.0  956.03  5376.4  960.41  5392.3  961.74  5398.0  963.16  5426.5  966.76
#Mann=6,-1,0
  4604.2    0.05       0  4807.0    0.12       0  4990.5    0.07       0
  4994.5    0.12       0  5135.6    0.05       0  5398.0    0.12       0
Bank Sta=4990.5,4994.5
Exp/Cntr=0.3,0.1

Type RM Length L Ch R = 1,7731,232,232,232
BEGIN DESCRIPTION:
SHIP HOLLOW CREEK 15.0
END DESCRIPTION:
XS GIS Cut Line= 3
      2881805.71     10166653.15      2882078.18     10167023.97
      2882161.59     10167165.57
#Sta/Elev= 30
  4597.9  946.48  4640.7  944.09  4655.3  941.98  4720.1  936.60  4797.3  933.41
  4843.2  932.63  4875.6  932.18  4933.1  930.50  4956.2  931.84  4991.7  928.78
  5010.6  928.42  5010.8  925.42  5014.3  925.42  5014.6  928.42  5027.2  930.32
  5060.5  932.64  5062.9  934.20  5084.4  936.15  5100.0  939.51  5105.8  939.54
  5121.5  943.26  5134.2  943.48  5143.0  942.80  5158.6  946.07  5164.4  946.02
  5180.1  948.96  5201.5  950.36  5207.9  951.98  5217.2  952.64  5222.4  951.89
#Mann=6,-1,0
  4597.9    0.05       0  4843.2    0.12       0  4875.6    0.05       0
  5010.6    0.05       0  5014.6    0.05       0  5134.2    0.12       0
Bank Sta=5010.6,5014.6
Exp/Cntr=0.3,0.1

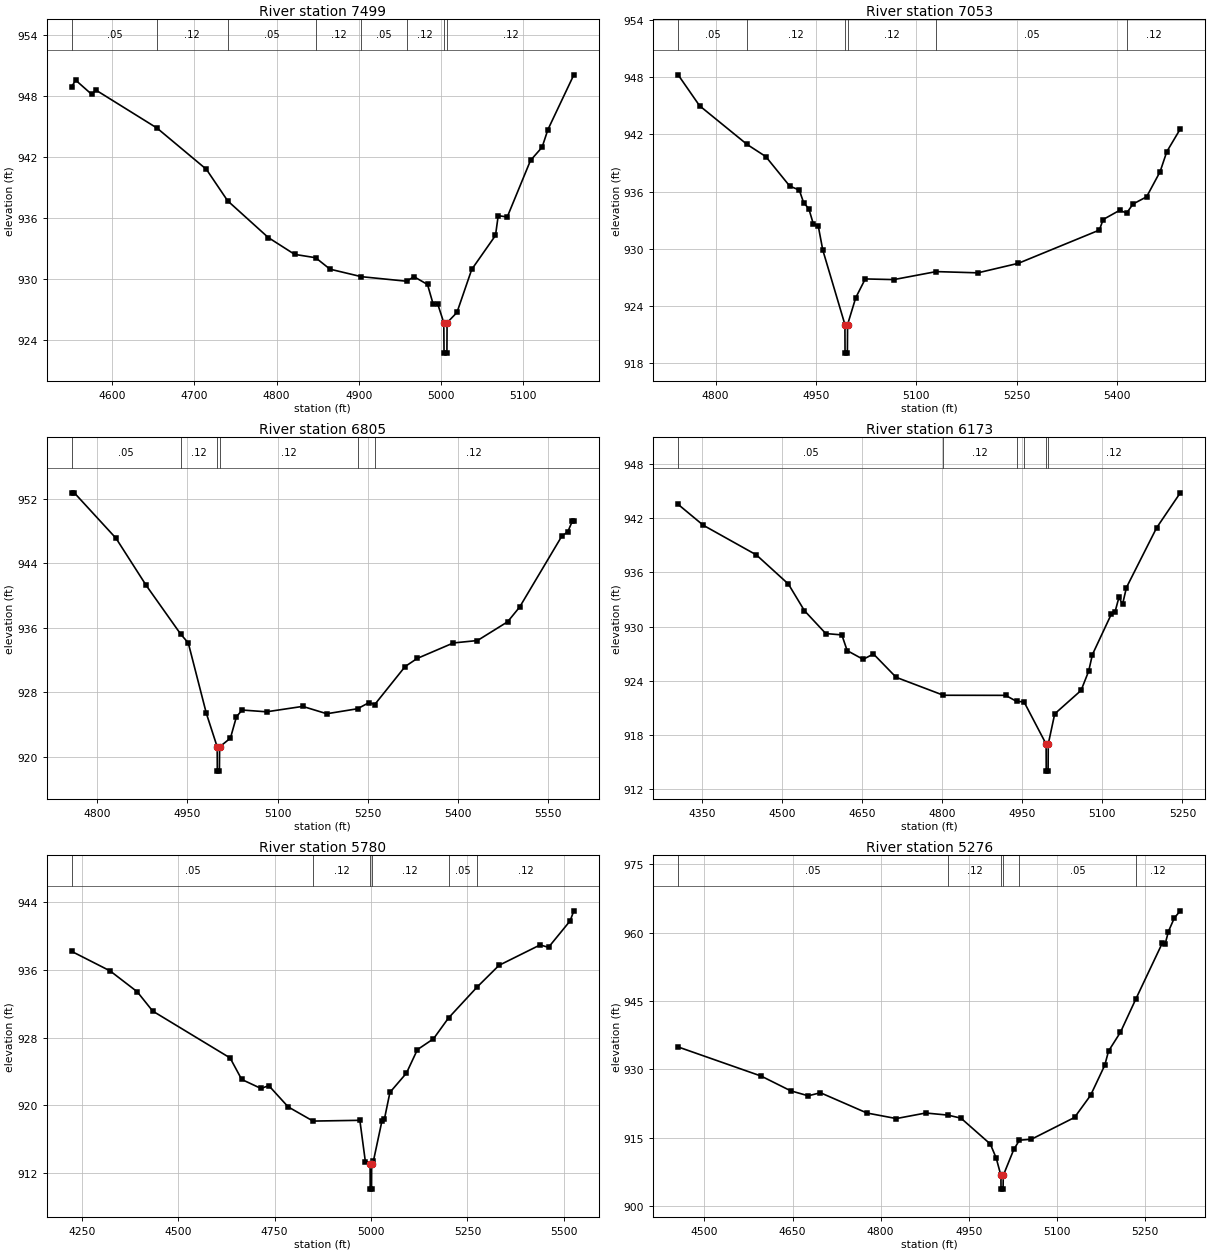
Type RM Length L Ch R = 1,7499,446,446,446
BEGIN DESCRIPTION:
Mapping XS 32488f2a
END DESCRIPTION:
XS GIS Cut Line= 4
      2881660.39     10166629.70      2881793.77     10166978.86
      2881852.62     10167114.20      2881914.96     10167178.49
#Sta/Elev= 30
  4550.7  948.94  4555.6  949.58  4575.0  948.19  4580.3  948.60  4654.5  944.86
  4714.6  940.79  4740.5  937.68  4789.9  934.06  4822.0  932.40  4847.5  932.07
  4865.0  930.94  4903.2  930.20  4958.3  929.75  4967.1  930.20  4983.6  929.43
  4990.5  927.48  4996.0  927.51  5003.4  925.66  5003.7  922.66  5007.2  922.66
  5007.4  925.66  5019.4  926.67  5037.4  930.92  5066.3  934.27  5069.6  936.22
  5080.6  936.09  5108.9  941.67  5123.0  942.97  5130.0  944.70  5161.6  950.11
#Mann=8,-1,0
  4550.7    0.05       0  4654.5    0.12       0  4740.5    0.05       0
  4847.5    0.12       0  4903.2    0.05       0  4958.3    0.12       0
  5003.4    0.07       0  5007.4    0.12       0
Bank Sta=5003.4,5007.4
Exp/Cntr=0.3,0.1

Type RM Length L Ch R = 1,7053,248,248,248
BEGIN DESCRIPTION:
SHIP HOLLOW CREEK 14.0
END DESCRIPTION:
XS GIS Cut Line= 3
      2881197.47     10166916.07      2881464.25     10167151.46
      2881855.67     10167203.11
#Sta/Elev= 30
  4744.0  948.26  4776.1  945.01  4847.1  940.95  4875.0  939.68  4910.8  936.58
  4925.1  936.16  4931.7  934.82  4939.3  934.21  4946.0  932.63  4953.5  932.37
  4960.2  929.87  4993.3  922.04  4993.5  919.04  4997.0  919.04  4997.3  922.04
  5009.5  924.86  5023.7  926.83  5066.4  926.76  5129.8  927.60  5192.0  927.47
  5252.5  928.47  5373.6  931.96  5379.3  933.07  5403.8  934.03  5414.4  933.75
  5424.0  934.70  5444.2  935.45  5464.4  938.09  5474.4  940.19  5494.6  942.58
#Mann=6,-1,0
  4744.0    0.05       0  4847.1    0.12       0  4993.3    0.07       0
  4997.3    0.12       0  5129.8    0.05       0  5414.4    0.12       0
Bank Sta=4993.3,4997.3
Exp/Cntr=0.3,0.1

Type RM Length L Ch R = 1,6805,632,632,632
BEGIN DESCRIPTION:
SHIP HOLLOW CREEK 13.0
END DESCRIPTION:
XS GIS Cut Line= 3
      2881071.98     10167304.46      2881417.18     10167284.84
      2881905.69     10167253.11
#Sta/Elev= 30
  4757.4  952.71  4761.8  952.71  4831.2  947.08  4881.3  941.25  4938.9  935.19
  4951.4  934.11  4981.5  925.37  4999.5  921.23  4999.7  918.23  5003.2  918.23
  5003.5  921.23  5021.5  922.32  5031.5  924.97  5041.0  925.80  5081.6  925.58
  5141.7  926.25  5181.8  925.34  5233.0  925.96  5252.0  926.72  5261.5  926.48
  5312.1  931.19  5332.1  932.19  5392.3  934.11  5432.4  934.41  5482.5  936.73
  5502.5  938.55  5572.6  947.33  5582.7  947.90  5590.2  949.20  5592.7  949.20
#Mann=6,-1,0
  4757.4    0.05       0  4938.9    0.12       0  4999.5    0.07       0
  5003.5    0.12       0  5233.0    0.05       0  5261.5    0.12       0
Bank Sta=4999.5,5003.5
Exp/Cntr=0.3,0.1

Type RM Length L Ch R = 1,6173,393,393,393
BEGIN DESCRIPTION:
Mapping XS 5ec4b791
END DESCRIPTION:
XS GIS Cut Line= 3
      2881109.25     10167686.94      2881464.25     10167696.74
      2881884.01     10167288.76
#Sta/Elev= 30
  4305.4  943.55  4352.4  941.24  4451.9  937.95  4511.9  934.72  4541.9  931.77
  4581.9  929.23  4612.0  929.08  4622.0  927.34  4652.0  926.37  4671.2  926.97
  4713.7  924.38  4802.3  922.39  4918.7  922.38  4939.3  921.71  4953.2  921.66
  4994.6  916.98  4994.8  913.98  4998.3  913.98  4998.6  916.98  5010.7  920.33
  5060.1  922.93  5074.3  925.07  5081.3  926.90  5116.7  931.38  5123.7  931.64
  5130.9  933.23  5137.8  932.49  5145.0  934.33  5201.6  940.96  5245.9  944.83
#Mann=6,-1,0
  4305.4    0.05       0  4802.3    0.12       0  4939.3    0.05       0
  4953.2    0.12       0  4994.6    0.07       0  4998.6    0.12       0
Bank Sta=4994.6,4998.6
Exp/Cntr=0.3,0.1

Type RM Length L Ch R = 1,5780,504,504,504
BEGIN DESCRIPTION:
SHIP HOLLOW CREEK 12.0
END DESCRIPTION:
XS GIS Cut Line= 3
      2881156.32     10167822.27      2881821.23     10167761.47
      2882303.46     10167347.85
#Sta/Elev= 30
  4223.2  938.20  4323.0  935.89  4393.3  933.43  4433.4  931.15  4634.3  925.61
  4664.4  923.07  4714.6  922.00  4734.7  922.34  4784.9  919.83  4849.5  918.15
  4971.0  918.24  4985.3  913.35  4997.6  913.11  4997.8  910.11  5001.3  910.11
  5001.6  913.11  5006.2  913.44  5028.1  918.12  5034.7  918.38  5049.0  921.54
  5091.8  923.81  5120.3  926.59  5162.0  927.87  5201.0  930.33  5274.9  933.97
  5332.1  936.55  5438.6  938.96  5460.5  938.68  5516.5  941.80  5526.2  942.99
#Mann=6,-1,0
  4223.2    0.05       0  4849.5    0.12       0  4997.6    0.07       0
  5001.6    0.12       0  5201.0    0.05       0  5274.9    0.12       0
Bank Sta=4997.6,5001.6
Exp/Cntr=0.3,0.1

Type RM Length L Ch R = 1,5276,319,319,319
BEGIN DESCRIPTION:
SHIP HOLLOW CREEK 11.0
END DESCRIPTION:
XS GIS Cut Line= 3
      2881254.34     10168102.76      2881925.77     10168117.85
      2882105.65     10168153.10
#Sta/Elev= 30
  4455.2  934.89  4596.6  928.49  4646.6  925.27  4676.6  924.16  4697.5  924.83
  4776.6  920.38  4826.6  919.16  4876.7  920.38  4914.4  919.92  4936.7  919.25
  4986.7  913.56  4996.7  910.48  5004.7  906.66  5004.9  903.66  5008.4  903.66
  5008.7  906.66  5026.7  912.39  5036.3  914.41  5056.7  914.62  5130.0  919.40
  5157.3  924.25  5181.5  930.87  5187.9  933.98  5208.2  938.12  5234.8  945.53
  5279.3  957.66  5284.4  957.54  5289.8  960.23  5299.9  963.22  5310.1  964.79
#Mann=6,-1,0
  4455.2    0.05       0  4914.4    0.12       0  5004.7    0.07       0
  5008.7    0.12       0  5036.3    0.05       0  5234.8    0.12       0
Bank Sta=5004.7,5008.7
Exp/Cntr=0.3,0.1

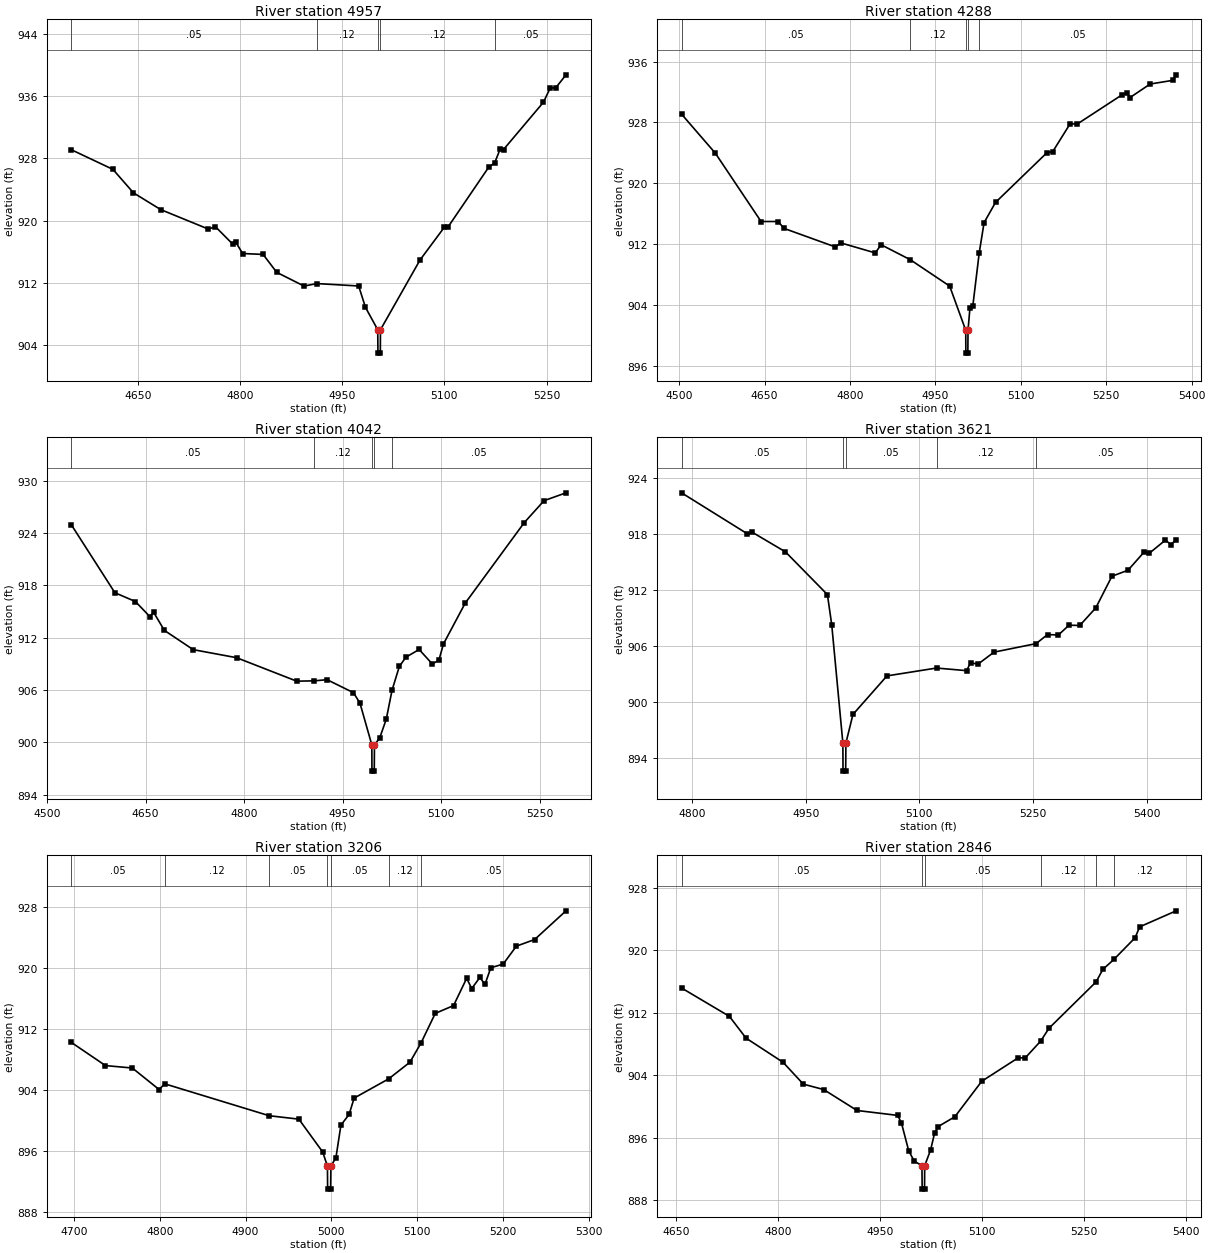
Type RM Length L Ch R = 1,4957,669,669,669
BEGIN DESCRIPTION:
SHIP HOLLOW CREEK 10.0
END DESCRIPTION:
XS GIS Cut Line= 3
      2881334.81     10168402.86      2881882.04     10168438.17
      2882058.56     10168416.59
#Sta/Elev= 30
  4552.3  929.12  4613.3  926.60  4643.4  923.59  4683.4  921.44  4753.6  918.93
  4763.6  919.26  4788.9  917.03  4793.9  917.22  4803.7  915.80  4833.8  915.68
  4853.8  913.38  4893.9  911.62  4912.6  911.94  4974.1  911.63  4984.1  908.88
  5002.1  906.01  5002.4  903.01  5005.9  903.01  5006.1  906.01  5064.2  914.97
  5099.6  919.14  5105.2  919.19  5164.8  926.85  5173.9  927.46  5181.7  929.18
  5186.8  929.15  5245.4  935.22  5255.5  937.08  5263.2  937.04  5278.5  938.74
#Mann=5,-1,0
  4552.3    0.05       0  4912.6    0.12       0  5002.1    0.07       0
  5006.1    0.12       0  5173.9    0.05       0
Bank Sta=5002.1,5006.1
Exp/Cntr=0.3,0.1

Type RM Length L Ch R = 1,4288,246,246,246
BEGIN DESCRIPTION:
SHIP HOLLOW CREEK 9.0
END DESCRIPTION:
XS GIS Cut Line= 3
      2881346.56     10168904.99      2881756.51     10168938.33
      2882211.07     10168889.35
#Sta/Elev= 30
  4504.3  929.09  4563.6  923.96  4643.9  914.98  4674.0  914.98  4684.0  914.08
  4774.3  911.64  4784.3  912.16  4844.5  910.85  4854.6  911.93  4905.9  909.96
  4975.1  906.49  5003.3  900.68  5003.5  897.68  5007.0  897.68  5007.3  900.68
  5010.7  903.62  5015.7  903.86  5027.0  910.87  5035.5  914.83  5055.6  917.49
  5146.1  924.04  5156.2  924.18  5186.3  927.79  5199.5  927.81  5276.9  931.59
  5286.4  931.90  5291.5  931.26  5327.1  933.05  5367.4  933.54  5372.8  934.26
#Mann=5,-1,0
  4504.3    0.05       0  4905.9    0.12       0  5003.3    0.07       0
  5007.3    0.12       0  5027.0    0.05       0
Bank Sta=5003.3,5007.3
Exp/Cntr=0.3,0.1

Type RM Length L Ch R = 1,4042,421,421,421
BEGIN DESCRIPTION:
SHIP HOLLOW CREEK 8.0
END DESCRIPTION:
XS GIS Cut Line= 3
      2881417.20     10169305.11      2881650.59     10169181.55
      2882139.03     10169159.97
#Sta/Elev= 30
  4537.1  924.92  4603.3  917.15  4634.6  916.14  4656.6  914.41  4662.2  914.92
  4678.6  912.84  4722.6  910.63  4788.6  909.71  4880.2  907.02  4906.8  907.06
  4926.4  907.19  4966.4  905.71  4976.4  904.52  4994.5  899.72  4994.7  896.72
  4998.2  896.72  4998.5  899.72  5006.5  900.52  5016.5  902.67  5025.3  905.99
  5036.5  908.73  5046.5  909.77  5066.5  910.65  5086.6  908.99  5096.6  909.43
  5103.6  911.29  5136.6  915.95  5226.7  925.19  5256.7  927.69  5290.1  928.59
#Mann=5,-1,0
  4537.1    0.05       0  4906.8    0.12       0  4994.5    0.07       0
  4998.5    0.12       0  5025.3    0.05       0
Bank Sta=4994.5,4998.5
Exp/Cntr=0.3,0.1

Type RM Length L Ch R = 1,3621,415,415,415
BEGIN DESCRIPTION:
SHIP HOLLOW CREEK 7.0
END DESCRIPTION:
XS GIS Cut Line= 3
      2881574.06     10169668.00      2881917.34     10169493.42
      2882107.59     10169305.13
#Sta/Elev= 30
  4786.2  922.39  4873.2  918.00  4878.8  918.21  4923.3  916.08  4978.7  911.51
  4984.4  908.29  4999.1  895.64  4999.3  892.64  5002.8  892.64  5003.1  895.64
  5012.4  898.70  5057.3  902.82  5122.7  903.66  5162.4  903.38  5167.6  904.22
  5177.5  904.08  5198.6  905.36  5254.1  906.27  5269.3  907.24  5283.5  907.19
  5297.6  908.24  5311.8  908.21  5333.0  910.10  5354.2  913.47  5375.5  914.12
  5396.6  916.05  5403.7  915.94  5424.9  917.34  5432.0  916.86  5439.0  917.36
#Mann=5,-1,0
  4786.2    0.05       0  4999.1    0.05       0  5003.1    0.05       0
  5122.7    0.12       0  5254.1    0.05       0
Bank Sta=4999.1,5003.1
Exp/Cntr=0.3,0.1

Type RM Length L Ch R = 1,3206,360,360,360
BEGIN DESCRIPTION:
SHIP HOLLOW CREEK 6.0
END DESCRIPTION:
XS GIS Cut Line= 3
      2881856.56     10169862.16      2881993.84     10169815.09
      2882360.16     10169587.86
#Sta/Elev= 30
  4697.1  910.21  4736.8  907.18  4768.1  906.86  4799.3  904.04  4805.8  904.79
  4927.5  900.61  4962.1  900.16  4989.9  895.85  4995.4  893.99  4995.6  890.99
  4999.1  890.99  4999.4  893.99  5005.3  895.12  5011.1  899.38  5020.6  900.77
  5026.5  902.92  5066.7  905.44  5091.5  907.62  5104.4  910.14  5121.0  914.02
  5142.3  915.04  5157.6  918.62  5163.5  917.27  5173.0  918.74  5178.9  917.81
  5185.7  920.00  5200.1  920.48  5215.5  922.83  5236.8  923.70  5273.3  927.46
#Mann=7,-1,0
  4697.1    0.05       0  4805.8    0.12       0  4927.5    0.05       0
  4995.4    0.05       0  4999.4    0.05       0  5066.7    0.12       0
  5104.4    0.05       0
Bank Sta=4995.4,4999.4
Exp/Cntr=0.3,0.1

Type RM Length L Ch R = 1,2846,474,474,474
BEGIN DESCRIPTION:
Mapping XS 194efb0a
END DESCRIPTION:
XS GIS Cut Line= 2
      2881854.59     10170203.45      2882531.95     10169939.16
#Sta/Elev= 30
  4658.6  915.16  4728.9  911.53  4753.4  908.74  4807.8  905.65  4837.6  902.85
  4867.5  902.16  4916.5  899.48  4976.2  898.85  4981.8  897.90  4992.5  894.32
  5000.7  892.99  5012.0  892.41  5012.3  889.41  5015.8  889.41  5016.0  892.41
  5024.7  894.42  5030.5  896.56  5035.9  897.42  5060.4  898.68  5099.9  903.22
  5153.6  906.23  5163.7  906.20  5186.5  908.36  5198.9  910.02  5268.0  915.94
  5277.8  917.53  5294.2  918.82  5325.3  921.59  5332.1  922.99  5385.7  925.04
#Mann=6,-1,0
  4658.6    0.05       0  5012.0    0.05       0  5016.0    0.05       0
  5186.5    0.12       0  5268.0    0.05       0  5294.2    0.12       0
Bank Sta=5012,5016
Exp/Cntr=0.3,0.1