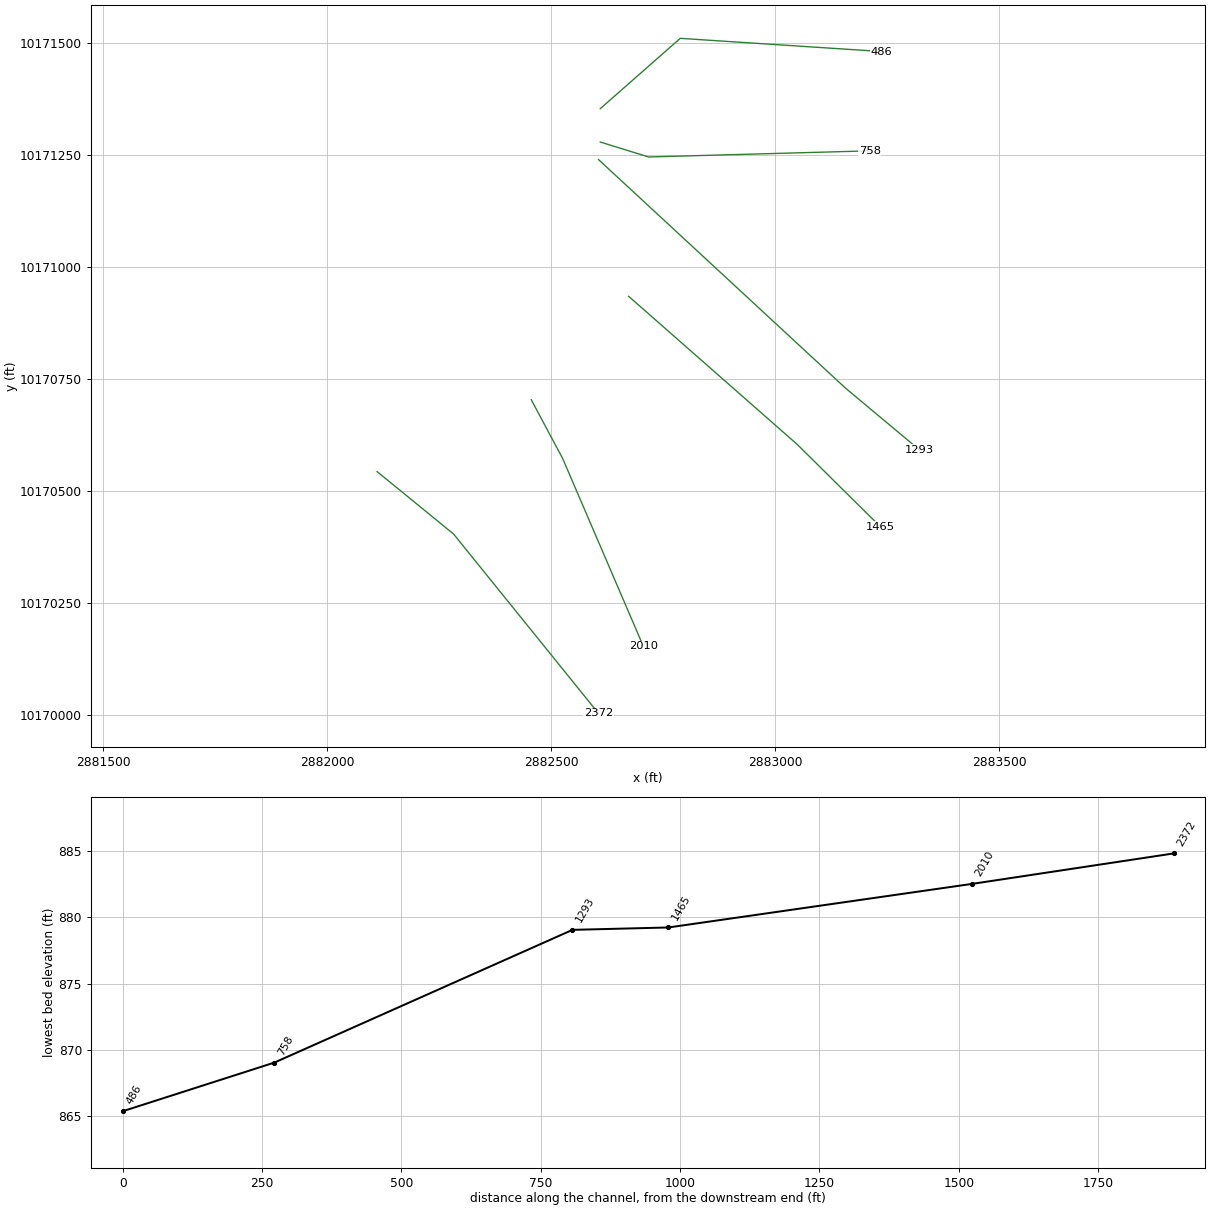
HEC-RAS study SHIP HOLLOW CREEK.prj: SHIP HOLLOW CREEK Base Level Engineering

--- SHIP HOLLOW CREEK.g01 (geometry) --- (continued)

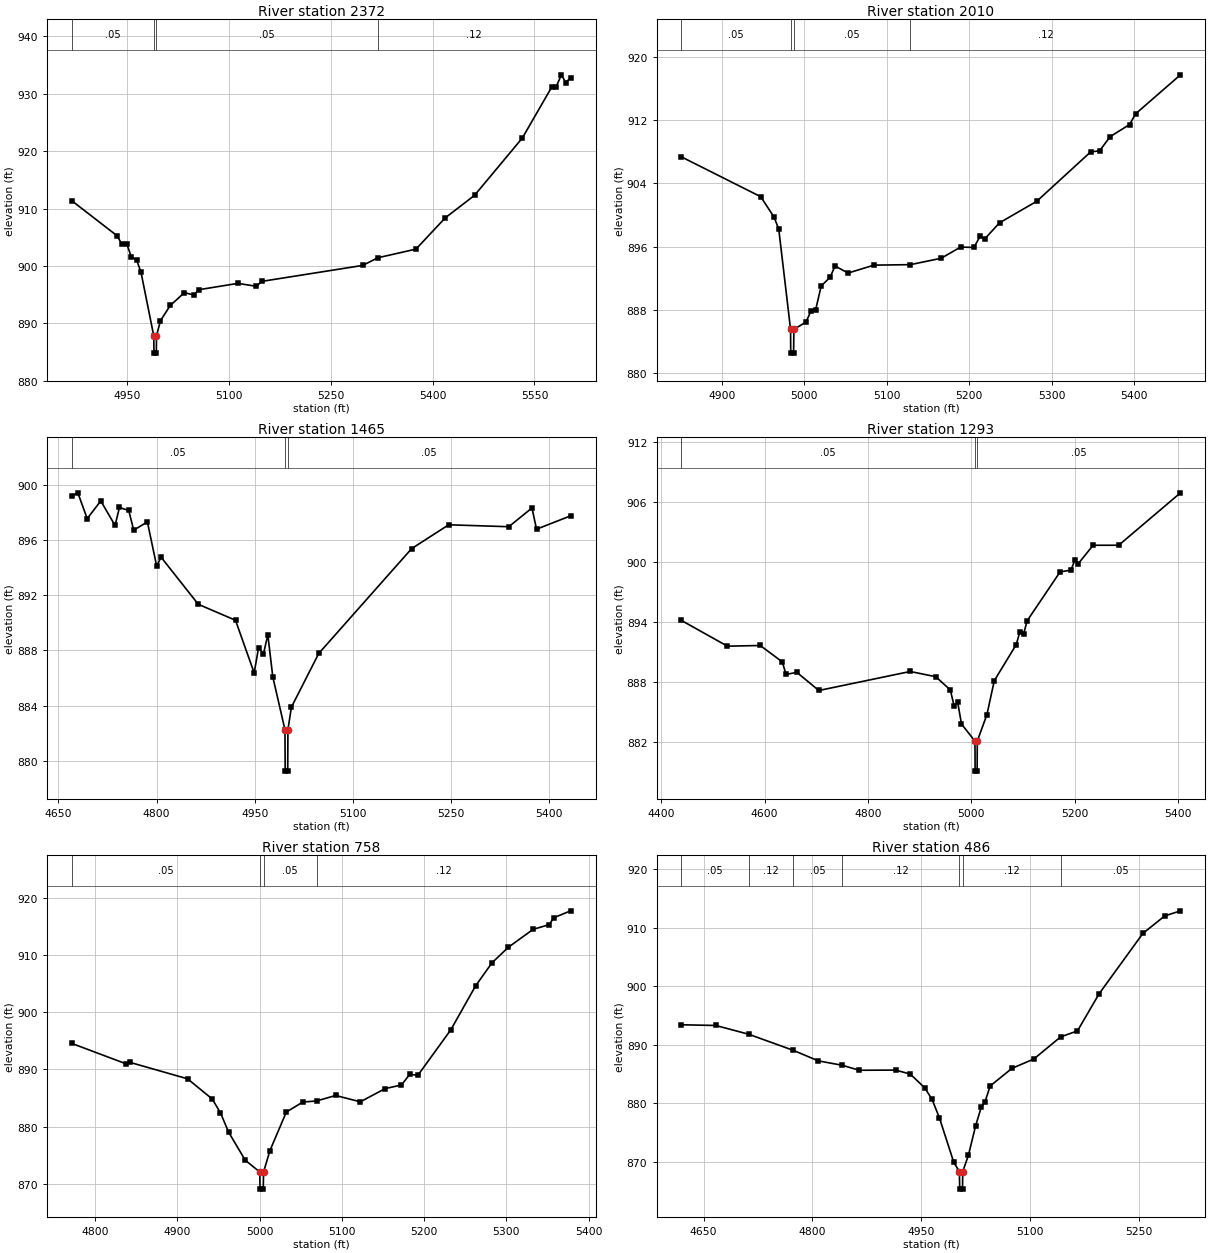
Type RM Length L Ch R = 1,2372,362,362,362
BEGIN DESCRIPTION:
SHIP HOLLOW CREEK 5.0
END DESCRIPTION:
XS GIS Cut Line= 3
      2882111.54     10170542.78      2882282.17     10170403.53
      2882605.68     10170003.12
#Sta/Elev= 30
  4868.3  911.40  4935.3  905.27  4941.8  903.92  4949.7  903.79  4956.2  901.60
  4964.0  901.07  4970.5  898.91  4989.3  887.83  4989.6  884.83  4993.1  884.83
  4993.3  887.83  4999.2  890.50  5013.6  893.13  5034.4  895.37  5048.8  894.94
  5055.2  895.87  5113.2  896.98  5140.5  896.47  5148.4  897.33  5297.1  900.11
  5319.3  901.44  5375.5  902.95  5418.6  908.39  5461.8  912.32  5532.2  922.31
  5575.3  931.14  5581.7  931.16  5589.7  933.31  5596.1  931.97  5603.3  932.82
#Mann=4,-1,0
  4868.3    0.05       0  4989.3    0.05       0  4993.3    0.05       0
  5319.3    0.12       0
Bank Sta=4989.3,4993.3
Exp/Cntr=0.3,0.1

Type RM Length L Ch R = 1,2010,545,545,545
BEGIN DESCRIPTION:
SHIP HOLLOW CREEK 4.0
END DESCRIPTION:
XS GIS Cut Line= 3
      2882455.66     10170703.15      2882525.75     10170572.00
      2882705.68     10170153.11
#Sta/Elev= 30
  4851.3  907.33  4947.3  902.30  4963.5  899.72  4969.2  898.19  4983.5  885.53
  4983.7  882.53  4987.2  882.53  4987.5  885.53  5002.1  886.45  5008.4  887.88
  5013.8  887.97  5020.6  891.01  5031.4  892.12  5037.4  893.54  5053.2  892.65
  5084.5  893.65  5128.6  893.71  5166.0  894.52  5189.6  895.94  5205.6  895.88
  5213.1  897.29  5218.6  896.95  5236.7  899.00  5281.8  901.72  5347.2  907.97
  5357.9  908.09  5370.7  909.89  5394.3  911.42  5401.5  912.77  5455.9  917.70
#Mann=4,-1,0
  4851.3    0.05       0  4983.5    0.05       0  4987.5    0.05       0
  5128.6    0.12       0
Bank Sta=4983.5,4987.5
Exp/Cntr=0.3,0.1

Type RM Length L Ch R = 1,1465,172,172,172
BEGIN DESCRIPTION:
SHIP HOLLOW CREEK 3.0
END DESCRIPTION:
XS GIS Cut Line= 3
      2882673.05     10170933.98      2883049.09     10170603.59
      2883235.43     10170419.21
#Sta/Elev= 30
  4670.2  899.21  4679.7  899.44  4694.0  897.57  4714.8  898.85  4736.6  897.07
  4743.3  898.38  4757.5  898.16  4765.1  896.73  4786.0  897.33  4800.2  894.12
  4806.9  894.77  4863.8  891.35  4920.7  890.19  4949.2  886.37  4955.9  888.19
  4963.4  887.74  4970.1  889.14  4977.7  886.08  4996.3  882.24  4996.6  879.24
  5000.5  879.24  5000.8  882.24  5006.1  883.88  5047.9  887.78  5189.9  895.39
  5246.5  897.12  5338.4  896.98  5373.8  898.34  5380.8  896.80  5432.9  897.77
#Mann=3,-1,0
  4670.2    0.05       0  4996.3    0.03       0  5000.8    0.05       0
Bank Sta=4996.3,5000.8
Exp/Cntr=0.3,0.1

Type RM Length L Ch R = 1,1293,535,535,535
BEGIN DESCRIPTION:
SHIP HOLLOW CREEK 2.0
END DESCRIPTION:
XS GIS Cut Line= 3
      2882605.78     10171239.13      2883156.97     10170729.12
      2883322.17     10170591.13
#Sta/Elev= 30
  4438.9  894.12  4528.0  891.55  4591.5  891.62  4634.1  889.98  4641.4  888.73
  4662.4  888.93  4704.9  887.12  4881.8  889.02  4931.2  888.50  4959.5  887.18
  4966.9  885.56  4973.7  885.96  4981.1  883.77  5007.2  882.06  5007.5  879.06
  5011.4  879.06  5011.7  882.06  5030.4  884.72  5044.6  888.10  5087.1  891.71
  5093.9  892.94  5101.3  892.74  5108.1  894.08  5172.1  898.98  5193.1  899.15
  5200.9  900.19  5207.4  899.81  5236.0  901.64  5285.5  901.64  5405.1  906.88
#Mann=3,-1,0
  4438.9    0.05       0  5007.2    0.05       0  5011.7    0.05       0
Bank Sta=5007.2,5011.7
Exp/Cntr=0.3,0.1

Type RM Length L Ch R = 1,758,272,272,272
BEGIN DESCRIPTION:
Mapping XS 0f789d6f
END DESCRIPTION:
XS GIS Cut Line= 3
      2882609.71     10171278.33      2882717.61     10171244.98
      2883211.28     10171258.69
#Sta/Elev= 30
  4771.4  894.57  4837.5  890.99  4842.8  891.22  4912.4  888.36  4942.4  884.82
  4952.4  882.40  4962.4  878.99  4982.5  874.11  5000.2  872.04  5000.5  869.04
  5004.4  869.04  5004.8  872.04  5012.5  875.77  5032.5  882.54  5052.5  884.29
  5069.2  884.48  5092.5  885.44  5122.5  884.33  5152.5  886.64  5172.5  887.28
  5182.5  889.13  5192.5  888.99  5232.5  896.94  5262.6  904.63  5282.6  908.68
  5302.6  911.41  5332.6  914.54  5352.4  915.37  5357.4  916.55  5378.2  917.78
#Mann=4,-1,0
  4771.4    0.05       0  5000.2    0.05       0  5004.8    0.05       0
  5069.2    0.12       0
Bank Sta=5000.2,5004.8
Exp/Cntr=0.3,0.1

Type RM Length L Ch R = 1,486,0,0,0
BEGIN DESCRIPTION:
SHIP HOLLOW CREEK 1.0
END DESCRIPTION:
XS GIS Cut Line= 3
      2882609.73     10171352.86      2882788.22     10171509.78
      2883237.40     10171480.35
#Sta/Elev= 30
  4619.4  893.41  4666.7  893.29  4711.9  891.80  4773.3  889.06  4808.1  887.25
  4841.0  886.50  4864.5  885.65  4914.6  885.68  4934.7  885.00  4954.7  882.66
  4964.8  880.69  4974.8  877.58  4994.8  869.93  5002.5  868.37  5002.9  865.37
  5006.8  865.37  5007.1  868.37  5014.9  871.13  5024.9  876.19  5032.7  879.38
  5037.7  880.22  5044.9  882.97  5075.0  885.98  5105.1  887.57  5142.1  891.35
  5165.2  892.36  5195.2  898.72  5255.4  909.00  5285.4  911.97  5307.2  912.85
#Mann=7,-1,0
  4619.4    0.05       0  4711.9    0.12       0  4773.3    0.05       0
  4841.0    0.12       0  5002.5    0.07       0  5007.1    0.12       0
  5142.1    0.05       0
Bank Sta=5002.5,5007.1
Exp/Cntr=0.3,0.1

Chan Stop Cuts=-1