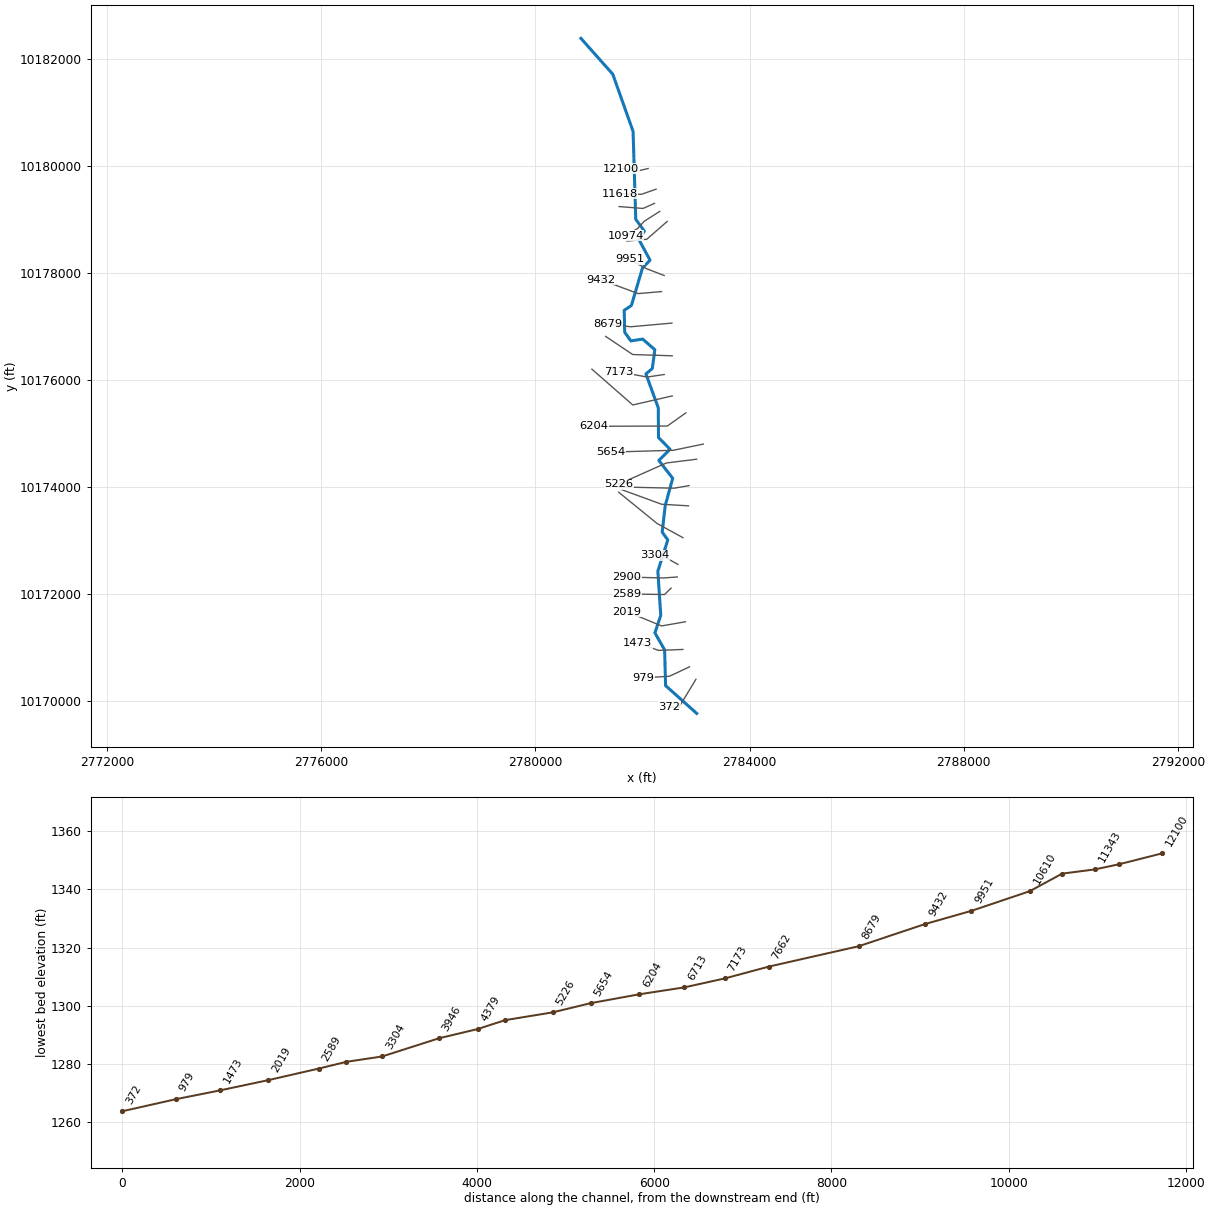
--- SILVERMINE CREEK.prj (project) ---

Proj Title=SILVERMINE CREEK Base Level Engineering
Current Plan=p01
Default Exp/Contr=0.3,0.1
English Units
Geom File=g01
Flow File=f01
Plan File=p01
BEGIN DESCRIPTION:
SILVERMINE CREEK
END DESCRIPTION:

--- SILVERMINE CREEK.p01 (plan) ---

Plan Title=Multiple Run
Short Identifier=Multiple
Geom File=g01
Flow File=f01
Subcritical Flow
K Sum by GR= 0
Std Step Tol= 0.01
Critical Tol= 0.01
Num of Std Step Trials= 20
Max Error Tol= 0.3
Flow Tol Ratio= 0.001
Split Flow NTrial= 30
Split Flow Tol= 0.02
Split Flow Ratio= 0.02
Log Output Level= 0
Friction Slope Method= 1
Unsteady Friction Slope Method= 2
Unsteady Bridges Friction Slope Method= 1
Parabolic Critical Depth
Global Vel Dist=  1 , 1 , 1
Global Log Level= 0
CheckData=True
Encroach Param= -1, 0, 0, 0
BEGIN DESCRIPTION:
Multiple Run
END DESCRIPTION:

--- SILVERMINE CREEK.f01 (steady flow) ---

Flow Title=Multiple
Number of Profiles=7
Profile Names=10-year,25-year,50-year,1pct_min,100-year,1pct_plu,500-year
River Rch & RM= SILVERMINE CREEK,Reach-1,12100
      88     175     278     146     442    1335    1194
River Rch & RM= SILVERMINE CREEK,Reach-1,6713
     102     209     337     179     540    1630    1479
River Rch & RM= SILVERMINE CREEK,Reach-1,2900
     166     357     588     318     962    2904    2733
Boundary for River Rch & Prof#=SILVERMINE CREEK,Reach-1,1
Up Type=0
Dn Type=3
Dn Slope=0.005
Boundary for River Rch & Prof#=SILVERMINE CREEK,Reach-1,2
Up Type=0
Dn Type=3
Dn Slope=0.005
Boundary for River Rch & Prof#=SILVERMINE CREEK,Reach-1,3
Up Type=0
Dn Type=3
Dn Slope=0.005
Boundary for River Rch & Prof#=SILVERMINE CREEK,Reach-1,4
Up Type=0
Dn Type=3
Dn Slope=0.005
Boundary for River Rch & Prof#=SILVERMINE CREEK,Reach-1,5
Up Type=0
Dn Type=3
Dn Slope=0.005
Boundary for River Rch & Prof#=SILVERMINE CREEK,Reach-1,6
Up Type=0
Dn Type=3
Dn Slope=0.005
Boundary for River Rch & Prof#=SILVERMINE CREEK,Reach-1,7
Up Type=0
Dn Type=3
Dn Slope=0.005

--- SILVERMINE CREEK.g01 (geometry) ---

Geom Title=Existing Conditions

River Reach=SILVERMINE CREEK,Reach-1
Reach XY= 30
      2780850.25     10182386.00      2781445.50     10181716.00
      2781824.50     10180647.00      2781874.50     10179004.00
      2782034.75     10178784.00      2781931.00     10178630.00
      2782141.50     10178240.00      2781999.75     10178094.00
      2781793.50     10177394.00      2781658.50     10177302.00
      2781668.00     10176893.00      2781783.25     10176731.00
      2782004.00     10176765.00      2782230.25     10176567.00
      2782184.00     10176216.00      2782064.50     10176114.00
      2782295.75     10175478.00      2782298.75     10174925.00
      2782514.50     10174706.00      2782305.00     10174497.00
      2782564.50     10174163.00      2782424.75     10173653.00
      2782368.00     10173157.00      2782472.75     10173012.00
      2782287.00     10172428.00      2782341.25     10171603.00
      2782232.25     10171273.00      2782413.25     10170958.00
      2782431.50     10170289.00      2783011.50     10169770.00

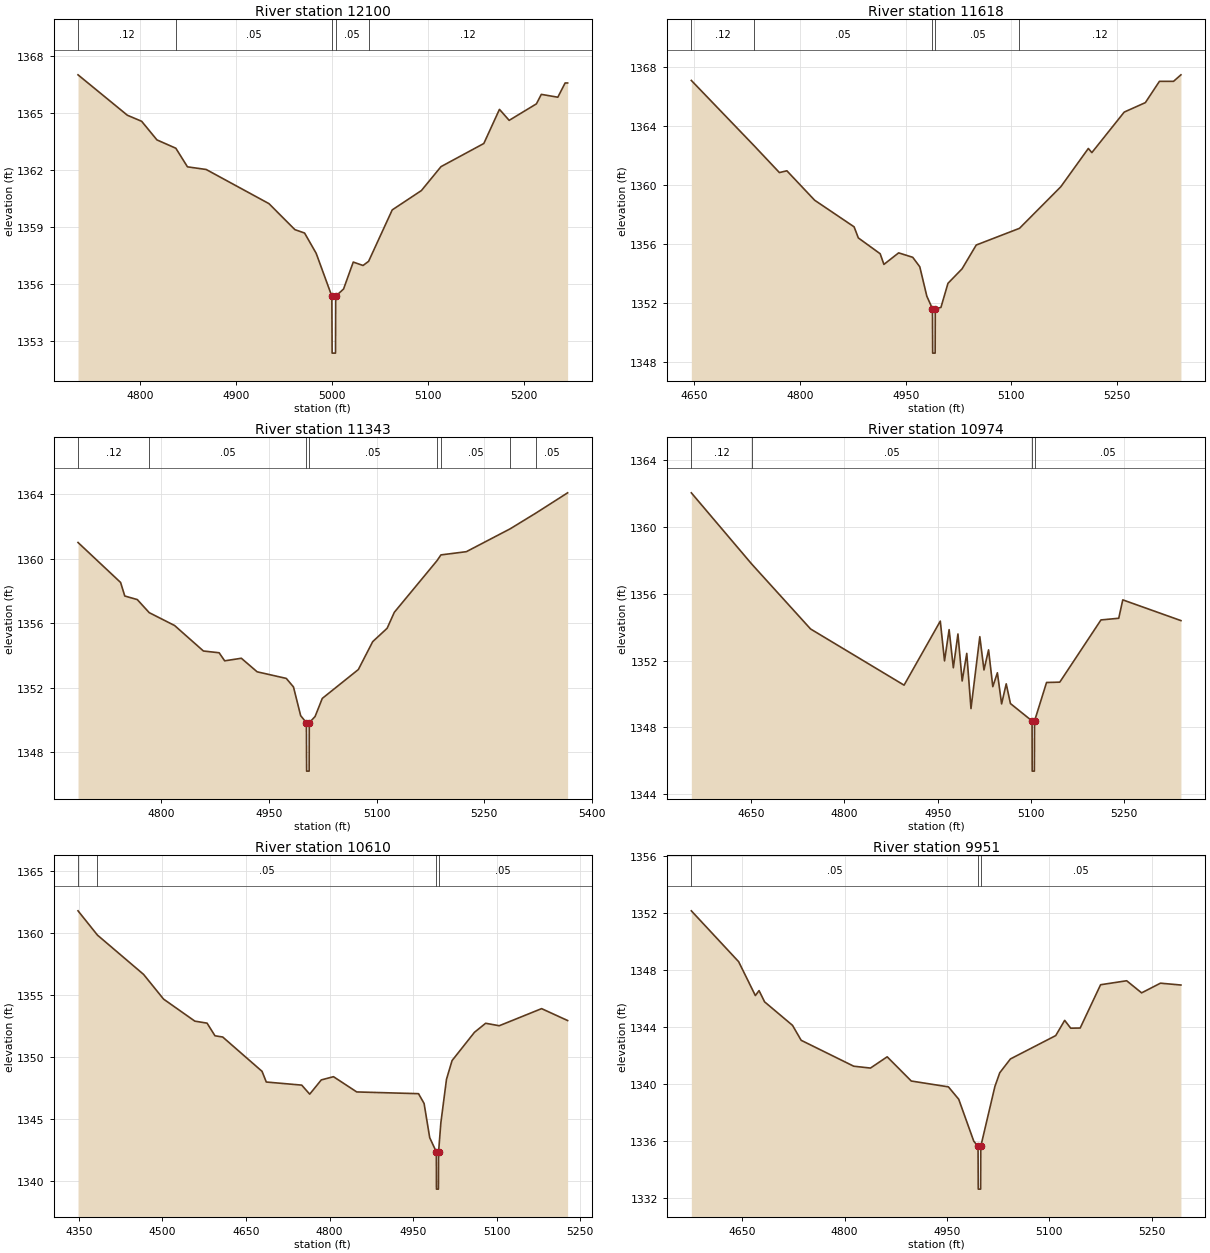
Type RM Length L Ch R = 1,12100,482,482,482
BEGIN DESCRIPTION:
SILVERMINE CREEK 24.0
END DESCRIPTION:
XS GIS Cut Line= 3
      2782105.70     10179953.12      2781893.62     10179903.51
      2781605.67     10179953.11
#Sta/Elev= 30
  4735.5 1367.01  4786.9 1364.88  4801.8 1364.56  4817.7 1363.58  4837.4 1363.14
  4849.5 1362.16  4869.0 1362.02  4934.4 1360.22  4961.4 1358.85  4971.5 1358.67
  4983.6 1357.60  4999.9 1355.34  5000.2 1352.34  5003.7 1352.34  5003.9 1355.34
  5012.1 1355.72  5022.2 1357.14  5032.4 1356.96  5038.2 1357.18  5062.8 1359.89
  5093.2 1360.91  5113.6 1362.17  5158.2 1363.39  5174.5 1365.19  5184.6 1364.61
  5213.0 1365.48  5218.1 1365.98  5235.3 1365.83  5242.9 1366.58  5245.5 1366.58
#Mann=5,-1,0
  4735.5    0.12       0  4837.4    0.05       0  4999.9    0.05       0
  5003.9    0.05       0  5038.2    0.12       0
Bank Sta=4999.9,5003.9
Exp/Cntr=0.3,0.1

Type RM Length L Ch R = 1,11618,275,275,275
BEGIN DESCRIPTION:
SILVERMINE CREEK 23.0
END DESCRIPTION:
XS GIS Cut Line= 3
      2782253.64     10179566.73      2781980.91     10179471.15
      2781575.23     10179481.29
#Sta/Elev= 30
  4645.8 1367.06  4734.2 1362.68  4770.8 1360.83  4781.4 1360.95  4820.8 1358.96
  4876.8 1357.16  4882.8 1356.41  4913.8 1355.34  4919.1 1354.62  4940.0 1355.40
  4960.0 1355.10  4970.0 1354.46  4980.0 1352.47  4988.0 1351.62  4988.3 1348.62
  4991.8 1348.62  4992.0 1351.62  5000.0 1351.71  5010.0 1353.34  5030.0 1354.32
  5050.1 1355.93  5111.5 1357.06  5170.1 1359.87  5209.2 1362.46  5214.2 1362.18
  5260.1 1364.92  5290.1 1365.56  5310.1 1367.00  5330.1 1367.00  5340.6 1367.44
#Mann=5,-1,0
  4645.8    0.12       0  4734.2    0.05       0  4988.0    0.03       0
  4992.0    0.05       0  5111.5    0.12       0
Bank Sta=4988,4992
Exp/Cntr=0.3,0.1

Type RM Length L Ch R = 1,11343,369,369,369
BEGIN DESCRIPTION:
SILVERMINE CREEK 22.0
END DESCRIPTION:
XS GIS Cut Line= 3
      2782225.16     10179302.09      2782010.72     10179206.59
      2781565.15     10179241.77
#Sta/Elev= 30
  4684.3 1361.02  4743.6 1358.54  4749.4 1357.70  4766.8 1357.48  4783.4 1356.67
  4818.8 1355.87  4858.9 1354.29  4880.8 1354.18  4888.5 1353.68  4911.7 1353.84
  4933.7 1353.00  4974.3 1352.59  4984.3 1352.06  4994.3 1350.28  5002.3 1349.84
  5002.6 1346.84  5006.1 1346.84  5006.3 1349.84  5014.4 1350.23  5024.4 1351.35
  5074.6 1353.14  5094.6 1354.87  5114.7 1355.70  5124.7 1356.69  5184.1 1359.89
  5189.6 1360.25  5225.0 1360.45  5286.1 1361.87  5322.4 1362.86  5366.0 1364.10
#Mann=8,-1,0
  4684.3    0.12       0  4783.4    0.05       0  5002.3    0.05       0
  5006.3    0.05       0  5184.1    0.12       0  5189.6    0.05       0
  5286.1    0.12       0  5322.4    0.05       0
Bank Sta=5002.3,5006.3
Exp/Cntr=0.3,0.1

Type RM Length L Ch R = 1,10974,364,364,364
BEGIN DESCRIPTION:
SILVERMINE CREEK 21.0
END DESCRIPTION:
XS GIS Cut Line= 4
      2782322.25     10179151.31      2782032.50     10178967.07
      2781908.55     10178831.40      2781685.75     10178695.71
#Sta/Elev= 30
  4553.6 1362.03  4650.6 1357.78  4745.5 1353.89  4896.0 1350.53  4954.3 1354.36
  4961.1 1351.98  4968.5 1353.85  4975.3 1351.57  4982.7 1353.59  4989.5 1350.78
  4996.9 1352.43  5003.7 1349.13  5017.9 1353.43  5024.6 1351.44  5032.0 1352.64
  5038.8 1350.44  5046.2 1351.27  5053.0 1349.41  5060.4 1350.61  5067.2 1349.43
  5102.0 1348.39  5102.2 1345.39  5105.7 1345.39  5106.0 1348.39  5125.3 1350.69
  5146.6 1350.71  5212.9 1354.43  5241.5 1354.53  5248.0 1355.63  5341.6 1354.39
#Mann=4,-1,0
  4553.6    0.12       0  4650.6    0.05       0  5102.0    0.05       0
  5106.0    0.05       0
Bank Sta=5102,5106
Exp/Cntr=0.3,0.1

Type RM Length L Ch R = 1,10610,659,659,659
BEGIN DESCRIPTION:
SILVERMINE CREEK 20.0
END DESCRIPTION:
XS GIS Cut Line= 3
      2782461.33     10178963.75      2782079.40     10178630.40
      2781709.14     10178597.04
#Sta/Elev= 30
  4348.5 1361.82  4383.4 1359.86  4466.2 1356.69  4502.0 1354.70  4558.2 1352.92
  4580.1 1352.76  4594.3 1351.74  4608.2 1351.64  4678.8 1348.87  4686.4 1348.01
  4750.0 1347.76  4764.3 1347.03  4785.1 1348.18  4807.0 1348.44  4848.7 1347.21
  4959.6 1347.07  4969.6 1346.28  4979.7 1343.52  4991.6 1342.37  4991.8 1339.37
  4995.3 1339.37  4995.6 1342.37  4999.7 1344.72  5009.8 1348.23  5019.8 1349.74
  5060.0 1352.02  5080.1 1352.75  5104.5 1352.55  5180.5 1353.93  5227.2 1352.97
#Mann=4,-1,0
  4348.5    0.12       0  4383.4    0.05       0  4991.6    0.05       0
  4995.6    0.05       0
Bank Sta=4991.6,4995.6
Exp/Cntr=0.3,0.1

Type RM Length L Ch R = 1,9951,519,519,519
BEGIN DESCRIPTION:
SILVERMINE CREEK 19.0
END DESCRIPTION:
XS GIS Cut Line= 3
      2782405.66     10177953.12      2782072.70     10178082.68
      2781755.69     10178253.11
#Sta/Elev= 30
  4575.5 1352.14  4644.8 1348.57  4669.3 1346.19  4674.7 1346.54  4682.8 1345.75
  4723.7 1344.10  4736.4 1343.05  4813.4 1341.23  4837.9 1341.10  4862.4 1341.89
  4897.7 1340.19  4952.1 1339.78  4967.2 1338.91  4989.2 1335.97  4995.5 1335.60
  4995.8 1332.60  4999.3 1332.60  4999.5 1335.60  5020.2 1339.81  5027.3 1340.77
  5042.9 1341.74  5109.3 1343.38  5122.4 1344.45  5131.2 1343.90  5145.1 1343.91
  5175.0 1346.95  5213.2 1347.23  5235.1 1346.38  5262.7 1347.06  5292.7 1346.93
#Mann=3,-1,0
  4575.5    0.05       0  4995.5    0.03       0  4999.5    0.05       0
Bank Sta=4995.5,4999.5
Exp/Cntr=0.3,0.1

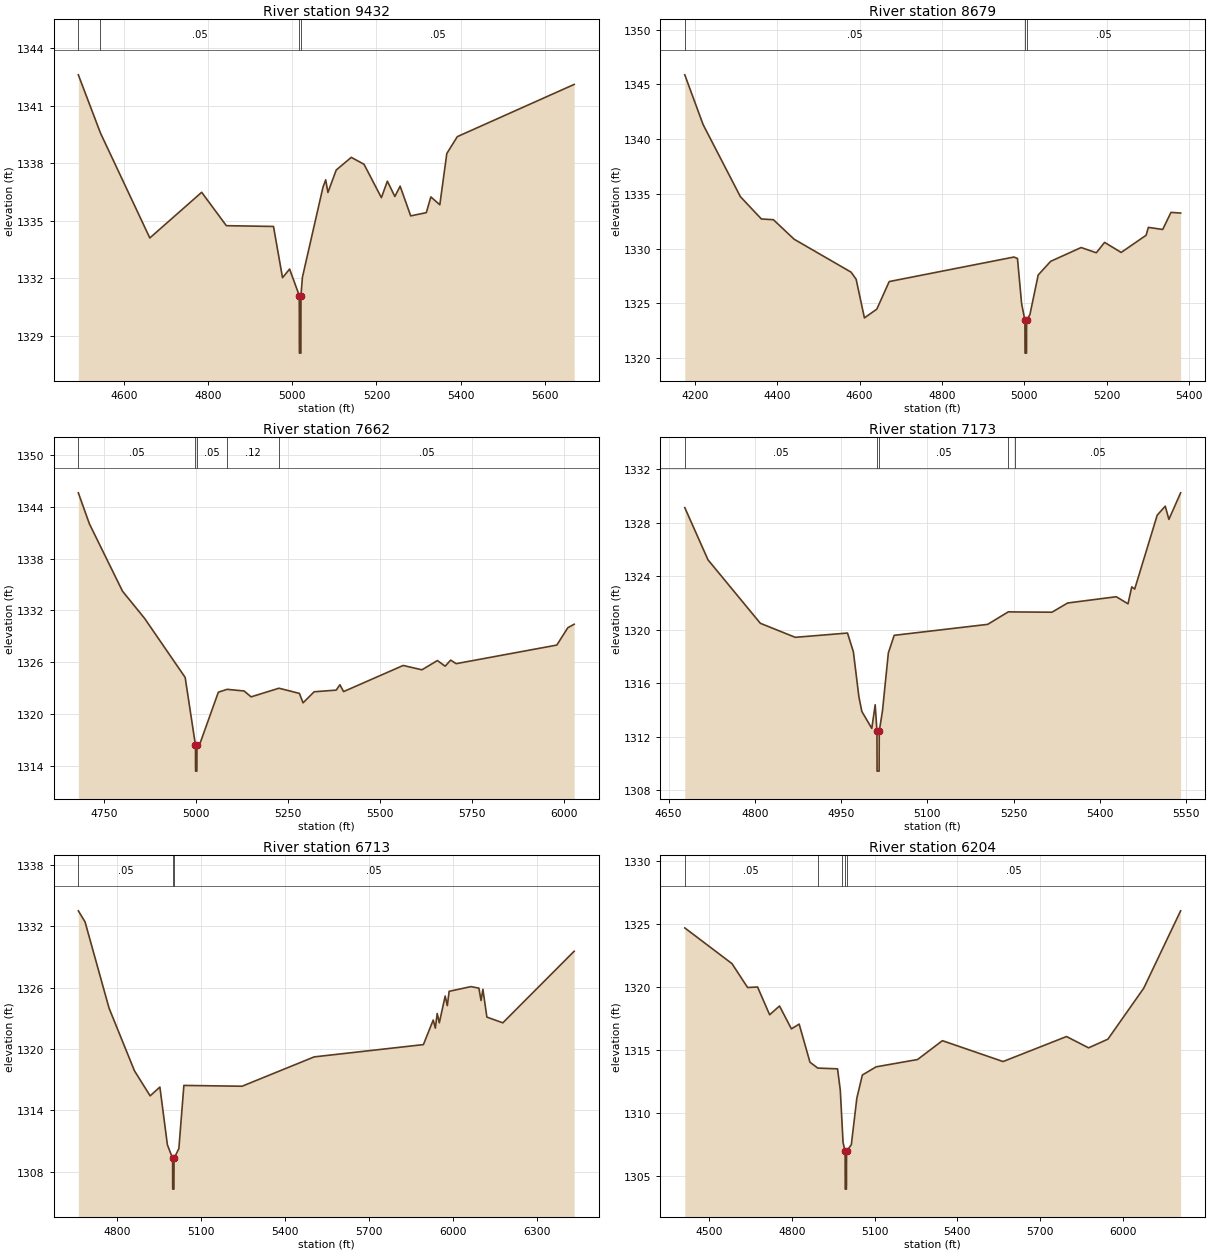
Type RM Length L Ch R = 1,9432,753,753,753
BEGIN DESCRIPTION:
SILVERMINE CREEK 18.0
END DESCRIPTION:
XS GIS Cut Line= 3
      2782355.73     10177653.12      2781920.27     10177615.36
      2781226.78     10177873.32
#Sta/Elev= 30
  4492.3 1342.60  4544.8 1339.57  4662.0 1334.10  4785.1 1336.48  4843.7 1334.74
  4955.6 1334.70  4977.0 1332.03  4993.8 1332.48  5016.8 1331.10  5017.1 1328.10
  5020.6 1328.10  5020.8 1331.10  5024.2 1332.05  5073.0 1336.74  5079.5 1337.13
  5084.8 1336.47  5104.5 1337.64  5140.2 1338.30  5170.5 1337.94  5211.7 1336.20
  5225.9 1337.06  5243.7 1336.26  5256.2 1336.80  5281.3 1335.25  5318.4 1335.42
  5329.1 1336.24  5350.4 1335.83  5367.0 1338.50  5392.0 1339.38  5669.3 1342.10
#Mann=4,-1,0
  4492.3    0.12       0  4544.8    0.05       0  5016.8    0.05       0
  5020.8    0.05       0
Bank Sta=5016.8,5020.8
Exp/Cntr=0.3,0.1

Type RM Length L Ch R = 1,8679,1017,1017,1017
BEGIN DESCRIPTION:
SILVERMINE CREEK 17.0
END DESCRIPTION:
XS GIS Cut Line= 3
      2782550.04     10177064.29      2781779.67     10176995.45
      2781352.47     10177047.53
#Sta/Elev= 30
  4175.6 1345.87  4220.1 1341.32  4310.5 1334.74  4361.5 1332.70  4390.8 1332.63
  4441.0 1330.85  4579.3 1327.84  4591.6 1327.19  4611.7 1323.66  4641.8 1324.46
  4671.9 1326.98  4974.6 1329.22  4983.3 1329.09  4993.4 1324.95  5001.4 1323.44
  5001.7 1320.44  5005.2 1320.44  5005.4 1323.44  5013.5 1323.96  5033.6 1327.58
  5063.9 1328.83  5137.9 1330.09  5174.7 1329.61  5194.8 1330.56  5235.1 1329.64
  5295.6 1331.21  5301.1 1331.93  5335.9 1331.74  5356.0 1333.30  5379.4 1333.24
#Mann=3,-1,0
  4175.6    0.05       0  5001.4    0.05       0  5005.4    0.05       0
Bank Sta=5001.4,5005.4
Exp/Cntr=0.3,0.1

Type RM Length L Ch R = 1,7662,489,489,489
BEGIN DESCRIPTION:
SILVERMINE CREEK 16.0
END DESCRIPTION:
XS GIS Cut Line= 3
      2782555.64     10176453.11      2781817.72     10176476.53
      2781312.55     10176815.04
#Sta/Elev= 30
  4680.3 1345.61  4710.3 1342.03  4800.3 1334.23  4860.4 1331.08  4970.4 1324.26
  4998.4 1316.42  4998.7 1313.42  5002.2 1313.42  5002.4 1316.42  5010.4 1316.59
  5060.5 1322.55  5084.4 1322.88  5130.5 1322.69  5149.4 1322.01  5225.2 1323.01
  5280.6 1322.41  5290.6 1321.32  5320.6 1322.60  5380.6 1322.79  5390.6 1323.41
  5400.6 1322.62  5562.3 1325.64  5613.3 1325.14  5655.4 1326.21  5676.4 1325.56
  5691.4 1326.26  5706.4 1325.85  5979.6 1328.00  6009.6 1330.01  6026.7 1330.41
#Mann=5,-1,0
  4680.3    0.05       0  4998.4    0.05       0  5002.4    0.05       0
  5084.4    0.12       0  5225.2    0.05       0
Bank Sta=4998.4,5002.4
Exp/Cntr=0.3,0.1

Type RM Length L Ch R = 1,7173,460,460,460
BEGIN DESCRIPTION:
SILVERMINE CREEK 15.0
END DESCRIPTION:
XS GIS Cut Line= 3
      2782405.68     10176103.11      2782087.25     10176056.00
      2781555.65     10176153.12
#Sta/Elev= 30
  4678.1 1329.14  4718.5 1325.23  4809.5 1320.48  4870.2 1319.43  4961.1 1319.75
  4971.3 1318.34  4980.9 1314.97  4986.0 1313.88  5003.3 1312.61  5009.2 1314.38
  5012.3 1312.41  5012.5 1309.41  5016.0 1309.41  5016.3 1312.41  5021.9 1313.92
  5032.1 1318.26  5042.3 1319.58  5204.9 1320.40  5240.8 1321.34  5252.0 1321.33
  5316.7 1321.31  5343.9 1322.00  5428.5 1322.47  5448.9 1321.94  5455.4 1323.21
  5460.5 1323.04  5499.7 1328.58  5513.7 1329.25  5520.0 1328.26  5540.4 1330.25
#Mann=5,-1,0
  4678.1    0.05       0  5012.3    0.05       0  5016.3    0.05       0
  5240.8    0.12       0  5252.0    0.05       0
Bank Sta=5012.3,5016.3
Exp/Cntr=0.3,0.1

Type RM Length L Ch R = 1,6713,509,509,509
BEGIN DESCRIPTION:
SILVERMINE CREEK 14.0
END DESCRIPTION:
XS GIS Cut Line= 3
      2782555.66     10175703.11      2781819.03     10175533.82
      2781055.72     10176203.08
#Sta/Elev= 30
  4662.0 1333.52  4686.0 1332.44  4771.7 1324.01  4862.5 1317.88  4918.5 1315.43
  4953.3 1316.29  4980.1 1310.65  4998.8 1309.31  4999.1 1306.31  5003.4 1306.31
  5003.8 1309.31  5021.1 1310.28  5039.0 1316.45  5246.8 1316.37  5504.5 1319.24
  5894.5 1320.44  5929.6 1322.84  5937.2 1322.05  5943.8 1323.48  5951.4 1322.57
  5972.3 1325.19  5979.9 1324.25  5986.5 1325.65  6064.4 1326.11  6092.8 1325.96
  6100.4 1324.75  6107.1 1325.84  6121.3 1323.13  6178.2 1322.57  6433.0 1329.57
#Mann=3,-1,0
  4662.0    0.05       0  4998.8    0.03       0  5003.8    0.05       0
Bank Sta=4998.8,5003.8
Exp/Cntr=0.3,0.1

Type RM Length L Ch R = 1,6204,550,550,550
BEGIN DESCRIPTION:
SILVERMINE CREEK 13.0
END DESCRIPTION:
XS GIS Cut Line= 3
      2782810.81     10175386.70      2782463.56     10175140.15
      2781092.04     10175134.95
#Sta/Elev= 30
  4412.1 1324.71  4583.2 1321.87  4639.7 1319.97  4675.9 1320.01  4719.7 1317.80
  4755.4 1318.50  4798.6 1316.68  4826.7 1317.06  4865.8 1314.03  4894.0 1313.56
  4965.8 1313.50  4975.8 1311.81  4981.9 1309.27  4985.8 1307.64  4993.3 1306.93
  4993.7 1303.93  4998.0 1303.93  4998.4 1306.93  5015.8 1307.47  5035.8 1311.17
  5055.8 1313.01  5105.8 1313.66  5255.8 1314.24  5345.9 1315.74  5565.9 1314.08
  5795.9 1316.07  5875.9 1315.17  5945.9 1315.86  6075.9 1319.92  6209.5 1326.07
#Mann=5,-1,0
  4412.1    0.05       0  4894.0    0.12       0  4981.9    0.05       0
  4993.3    0.05       0  4998.4    0.05       0
Bank Sta=4993.3,4998.4
Exp/Cntr=0.3,0.1

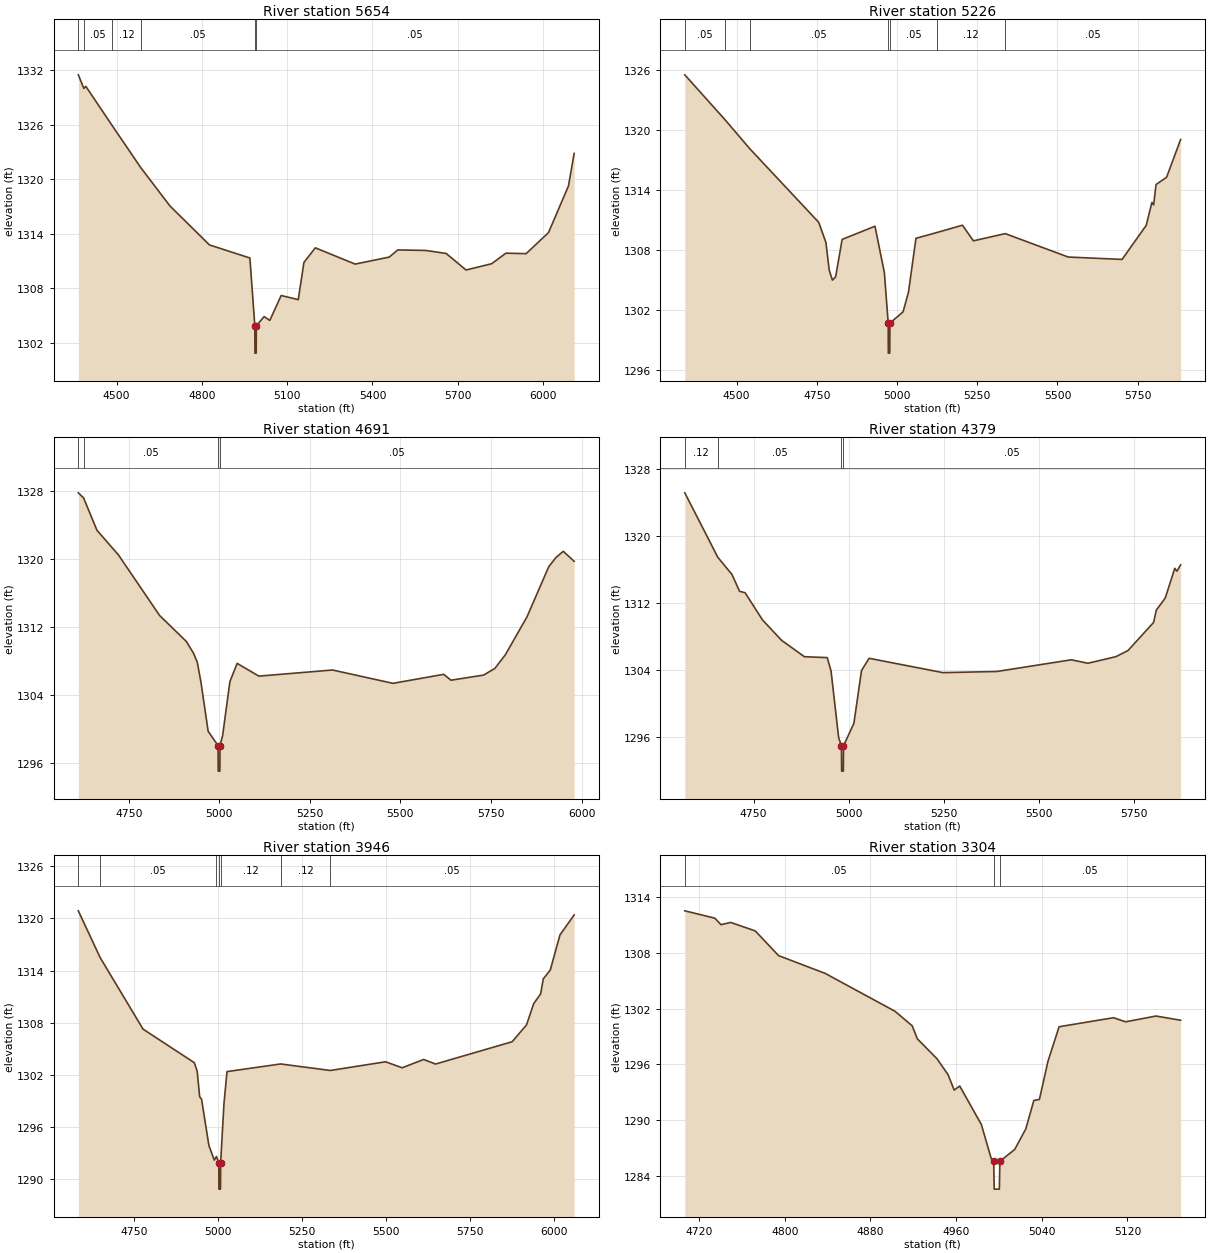
Type RM Length L Ch R = 1,5654,428,428,428
BEGIN DESCRIPTION:
SILVERMINE CREEK 12.0
END DESCRIPTION:
XS GIS Cut Line= 3
      2783137.14     10174803.34      2782576.40     10174687.03
      2781405.67     10174653.11
#Sta/Elev= 30
  4365.4 1331.50  4384.8 1330.00  4391.8 1330.23  4484.8 1325.90  4584.7 1321.30
  4687.6 1317.07  4826.5 1312.78  4968.8 1311.34  4986.2 1303.87  4986.6 1300.87
  4991.0 1300.87  4991.4 1303.87  5018.8 1304.89  5038.8 1304.47  5078.8 1307.21
  5138.9 1306.76  5158.9 1310.85  5198.9 1312.46  5339.0 1310.67  5459.0 1311.44
  5489.0 1312.23  5587.7 1312.17  5659.1 1311.84  5729.1 1310.02  5819.2 1310.71
  5869.2 1311.87  5940.4 1311.82  6019.2 1314.14  6089.3 1319.27  6109.3 1322.85
#Mann=6,-1,0
  4365.4    0.12       0  4384.8    0.05       0  4484.8    0.12       0
  4584.7    0.05       0  4986.2    0.03       0  4991.4    0.05       0
Bank Sta=4986.2,4991.4
Exp/Cntr=0.3,0.1

Type RM Length L Ch R = 1,5226,535,535,535
BEGIN DESCRIPTION:
SILVERMINE CREEK 11.0
END DESCRIPTION:
XS GIS Cut Line= 3
      2783012.17     10174520.36      2782444.46     10174449.18
      2781555.67     10174053.11
#Sta/Elev= 30
  4338.7 1325.54  4462.7 1321.10  4541.5 1318.14  4756.1 1310.79  4778.6 1308.76
  4788.7 1306.01  4798.8 1305.01  4808.8 1305.34  4829.0 1309.08  4931.4 1310.40
  4960.7 1305.75  4972.6 1300.71  4973.0 1297.71  4977.5 1297.71  4977.9 1300.71
  5019.0 1301.84  5035.9 1303.83  5059.1 1309.19  5125.4 1309.78  5204.0 1310.50
  5238.1 1308.94  5337.4 1309.66  5533.5 1307.32  5701.4 1307.08  5776.6 1310.48
  5794.4 1312.78  5799.8 1312.53  5807.3 1314.57  5840.1 1315.29  5883.9 1319.07
#Mann=7,-1,0
  4338.7    0.05       0  4462.7    0.12       0  4541.5    0.05       0
  4972.6    0.03       0  4977.9    0.05       0  5125.4    0.12       0
  5337.4    0.05       0
Bank Sta=4972.6,4977.9
Exp/Cntr=0.3,0.1

Type RM Length L Ch R = 1,4691,312,312,312
BEGIN DESCRIPTION:
SILVERMINE CREEK 10.0
END DESCRIPTION:
XS GIS Cut Line= 3
      2782869.83     10174027.31      2782593.77     10173978.70
      2781505.65     10174003.11
#Sta/Elev= 30
  4610.9 1327.80  4625.4 1327.20  4662.4 1323.39  4721.7 1320.49  4835.2 1313.37
  4909.3 1310.30  4929.3 1308.89  4939.3 1307.85  4949.3 1305.55  4969.3 1299.74
  4996.7 1298.05  4997.1 1295.05  5001.6 1295.05  5002.0 1298.05  5009.3 1299.26
  5029.3 1305.58  5049.3 1307.73  5109.3 1306.23  5312.7 1306.95  5479.4 1305.38
  5619.5 1306.44  5639.5 1305.75  5729.5 1306.35  5760.6 1307.13  5789.5 1308.73
  5849.5 1313.21  5909.5 1319.11  5929.6 1320.20  5949.6 1320.92  5979.6 1319.74
#Mann=4,-1,0
  4610.9    0.12       0  4625.4    0.05       0  4996.7    0.03       0
  5002.0    0.05       0
Bank Sta=4996.7,5002
Exp/Cntr=0.3,0.1

Type RM Length L Ch R = 1,4379,433,433,433
BEGIN DESCRIPTION:
SILVERMINE CREEK 9.0
END DESCRIPTION:
XS GIS Cut Line= 3
      2782859.40     10173648.83      2782357.65     10173678.35
      2781605.69     10173953.11
#Sta/Elev= 30
  4569.4 1325.12  4656.1 1317.45  4693.3 1315.40  4713.4 1313.39  4727.9 1313.22
  4773.5 1309.99  4823.6 1307.56  4883.7 1305.60  4943.8 1305.49  4953.8 1303.90
  4973.8 1295.95  4981.2 1294.97  4981.6 1291.97  4986.1 1291.97  4986.5 1294.97
  5013.9 1297.67  5033.9 1303.96  5053.9 1305.41  5248.0 1303.70  5390.0 1303.84
  5585.1 1305.23  5629.0 1304.82  5702.3 1305.60  5734.2 1306.33  5801.6 1309.68
  5808.7 1311.15  5832.1 1312.58  5857.3 1316.13  5862.7 1315.78  5872.6 1316.54
#Mann=4,-1,0
  4569.4    0.12       0  4656.1    0.05       0  4981.2    0.05       0
  4986.5    0.05       0
Bank Sta=4981.2,4986.5
Exp/Cntr=0.3,0.1

Type RM Length L Ch R = 1,3946,642,642,642
BEGIN DESCRIPTION:
SILVERMINE CREEK 8.0
END DESCRIPTION:
XS GIS Cut Line= 3
      2782755.66     10173053.12      2782272.58     10173318.97
      2781555.72     10173903.08
#Sta/Elev= 30
  4584.5 1320.87  4649.3 1315.50  4777.2 1307.25  4929.7 1303.39  4938.3 1302.43
  4945.7 1299.47  4951.4 1299.18  4973.2 1293.85  4989.3 1292.17  4995.7 1292.59
  5002.7 1291.83  5003.1 1288.83  5007.7 1288.83  5008.1 1291.83  5018.2 1298.75
  5027.2 1302.36  5186.9 1303.24  5334.6 1302.49  5499.1 1303.49  5548.6 1302.80
  5612.5 1303.76  5647.9 1303.23  5876.1 1305.80  5918.8 1307.74  5940.0 1310.17
  5960.8 1311.31  5968.7 1313.03  5989.6 1314.06  6018.3 1318.09  6060.6 1320.40
#Mann=7,-1,0
  4584.5    0.12       0  4649.3    0.05       0  4995.7    0.12       0
  5002.7    0.07       0  5008.1    0.12       0  5186.9    0.12       0
  5334.6    0.05       0
Bank Sta=5002.7,5008.1
Exp/Cntr=0.3,0.1

Type RM Length L Ch R = 1,3304,404,404,404
BEGIN DESCRIPTION:
SILVERMINE CREEK 7.0
END DESCRIPTION:
XS GIS Cut Line= 3
      2782663.24     10172553.34      2782472.24     10172659.25
      2782236.12     10172723.49
#Sta/Elev= 30
  4706.6 1312.51  4734.7 1311.72  4740.4 1311.02  4749.5 1311.26  4772.4 1310.35
  4794.2 1307.69  4837.7 1305.78  4903.0 1301.70  4919.0 1300.14  4923.8 1298.74
  4942.2 1296.59  4952.5 1294.88  4958.2 1293.23  4963.4 1293.66  4983.6 1289.52
  4992.8 1285.86  4995.1 1285.57  4995.6 1282.57  5000.4 1282.57  5000.9 1285.57
  5014.7 1286.83  5025.1 1289.05  5032.6 1292.11  5037.8 1292.22  5045.8 1296.32
  5056.2 1300.04  5107.0 1301.01  5118.3 1300.57  5146.7 1301.19  5169.7 1300.74
#Mann=3,-1,0
  4706.6    0.05       0  4995.1    0.05       0  5000.9    0.05       0
Bank Sta=4995.1,5000.9
Exp/Cntr=0.3,0.1

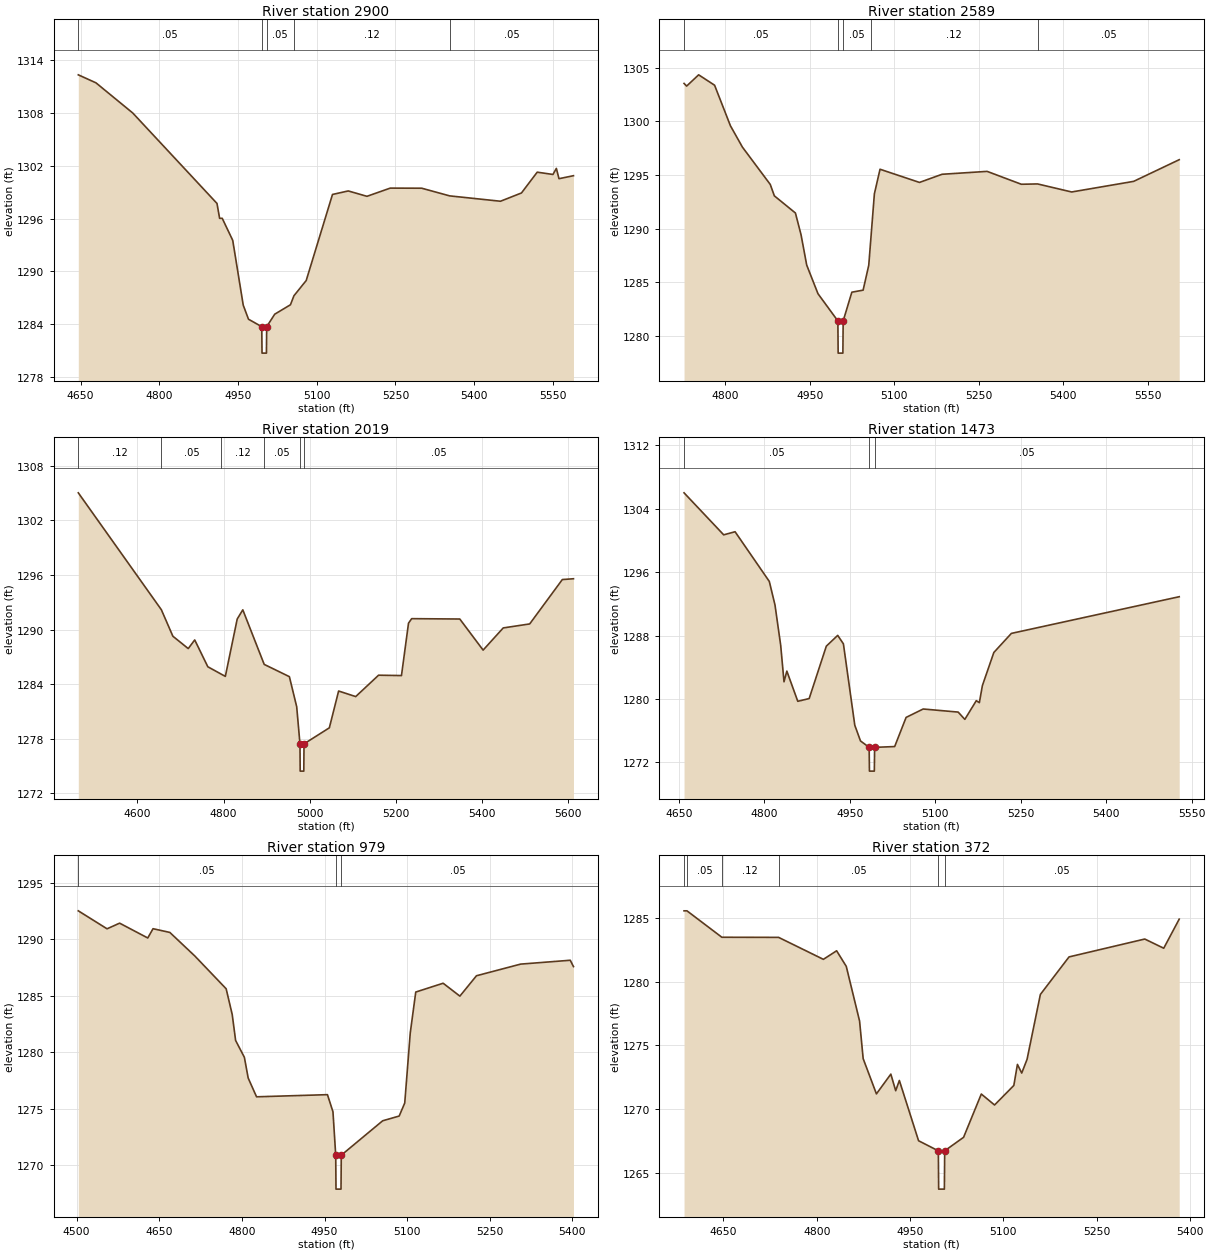
Type RM Length L Ch R = 1,2900,311,311,311
BEGIN DESCRIPTION:
SILVERMINE CREEK 6.0
END DESCRIPTION:
XS GIS Cut Line= 3
      2782649.31     10172318.97      2782380.56     10172300.32
      2781706.61     10172318.97
#Sta/Elev= 30
  4645.7 1312.31  4679.4 1311.40  4749.6 1307.97  4910.0 1297.71  4915.0 1296.02
  4920.0 1296.02  4940.0 1293.52  4960.0 1286.17  4970.0 1284.57  4995.3 1283.72
  4995.8 1280.72  5004.2 1280.72  5004.7 1283.72  5020.0 1285.14  5050.0 1286.21
  5056.6 1287.23  5080.0 1288.96  5130.1 1298.73  5160.1 1299.13  5195.8 1298.52
  5240.1 1299.45  5300.1 1299.44  5353.3 1298.57  5450.2 1297.96  5490.2 1298.90
  5520.2 1301.26  5550.2 1301.00  5556.7 1301.69  5561.7 1300.52  5589.3 1300.86
#Mann=5,-1,0
  4645.7    0.05       0  4995.3    0.05       0  5004.7    0.05       0
  5056.6    0.12       0  5353.3    0.05       0
Bank Sta=4995.3,5004.7
Exp/Cntr=0.3,0.1

Type RM Length L Ch R = 1,2589,570,570,570
BEGIN DESCRIPTION:
SILVERMINE CREEK 5.0
END DESCRIPTION:
XS GIS Cut Line= 3
      2782534.71     10172110.61      2782411.47     10171990.85
      2781704.92     10172003.00
#Sta/Elev= 30
  4727.2 1303.55  4731.8 1303.30  4753.1 1304.35  4781.4 1303.38  4809.5 1299.60
  4830.8 1297.61  4880.2 1294.13  4887.4 1293.07  4924.8 1291.47  4934.8 1289.44
  4944.8 1286.62  4964.8 1283.95  5000.1 1281.41  5000.6 1278.41  5009.0 1278.41
  5009.5 1281.41  5024.9 1284.09  5044.9 1284.28  5054.9 1286.60  5058.0 1288.66
  5064.9 1293.26  5074.9 1295.55  5144.9 1294.32  5184.9 1295.08  5264.9 1295.35
  5325.6 1294.15  5354.4 1294.18  5414.9 1293.43  5524.9 1294.42  5605.7 1296.44
#Mann=5,-1,0
  4727.2    0.05       0  5000.1    0.03       0  5009.5    0.05       0
  5058.0    0.12       0  5354.4    0.05       0
Bank Sta=5000.1,5009.5
Exp/Cntr=0.3,0.1

Type RM Length L Ch R = 1,2019,546,546,546
BEGIN DESCRIPTION:
SILVERMINE CREEK 4.0
END DESCRIPTION:
XS GIS Cut Line= 3
      2782802.12     10171482.17      2782355.92     10171404.04
      2781711.79     10171671.42
#Sta/Elev= 30
  4462.5 1305.04  4655.5 1292.18  4682.2 1289.27  4717.9 1287.91  4733.0 1288.86
  4763.4 1285.91  4794.9 1285.09  4804.1 1284.85  4831.7 1291.16  4844.7 1292.17
  4894.4 1286.17  4952.9 1284.82  4969.9 1281.51  4977.5 1277.43  4978.0 1274.43
  4986.4 1274.43  4986.9 1277.43  5045.7 1279.19  5067.3 1283.24  5107.0 1282.63
  5160.1 1284.98  5213.3 1284.94  5229.7 1290.71  5237.1 1291.20  5348.8 1291.16
  5403.0 1287.74  5449.7 1290.18  5511.2 1290.62  5587.0 1295.50  5612.9 1295.59
#Mann=6,-1,0
  4462.5    0.12       0  4655.5    0.05       0  4794.9    0.12       0
  4894.4    0.05       0  4977.5    0.05       0  4986.9    0.05       0
Bank Sta=4977.5,4986.9
Exp/Cntr=0.3,0.1

Type RM Length L Ch R = 1,1473,494,494,494
BEGIN DESCRIPTION:
SILVERMINE CREEK 3.0
END DESCRIPTION:
XS GIS Cut Line= 3
      2782755.26     10170964.81      2782298.63     10170947.45
      2781910.22     10171086.16
#Sta/Elev= 30
  4658.8 1306.02  4728.4 1300.72  4748.4 1301.11  4808.5 1294.84  4818.5 1291.86
  4828.5 1286.77  4834.3 1282.18  4839.3 1283.52  4858.5 1279.71  4878.5 1280.06
  4908.6 1286.67  4928.6 1288.03  4938.6 1286.96  4958.6 1276.69  4968.6 1274.71
  4983.8 1273.90  4984.3 1270.90  4992.9 1270.90  4993.4 1273.90  5028.6 1274.00
  5048.7 1277.68  5078.7 1278.74  5140.1 1278.35  5151.8 1277.43  5171.9 1279.79
  5177.3 1279.54  5182.6 1281.69  5202.7 1285.87  5233.5 1288.28  5528.2 1292.91
#Mann=3,-1,0
  4658.8    0.05       0  4983.8    0.03       0  4993.4    0.05       0
Bank Sta=4983.8,4993.4
Exp/Cntr=0.3,0.1

Type RM Length L Ch R = 1,979,607,607,607
BEGIN DESCRIPTION:
SILVERMINE CREEK 2.0
END DESCRIPTION:
XS GIS Cut Line= 3
      2782878.46     10170640.14      2782504.58     10170463.97
      2782019.94     10170433.61
#Sta/Elev= 30
  4503.0 1292.50  4555.2 1290.91  4578.0 1291.41  4629.1 1290.10  4638.7 1290.92
  4669.2 1290.59  4714.7 1288.50  4771.4 1285.61  4782.4 1283.34  4788.6 1281.04
  4804.5 1279.55  4811.4 1277.72  4826.6 1276.06  4955.3 1276.25  4965.3 1274.74
  4970.3 1270.90  4970.8 1267.90  4979.9 1267.90  4980.4 1270.90  5055.5 1273.94
  5085.5 1274.36  5095.6 1275.51  5105.6 1281.70  5115.6 1285.32  5165.3 1286.10
  5195.7 1284.96  5225.8 1286.76  5306.0 1287.79  5396.1 1288.13  5401.9 1287.57
#Mann=3,-1,0
  4503.0    0.05       0  4970.3    0.03       0  4980.4    0.05       0
Bank Sta=4970.3,4980.4
Exp/Cntr=0.3,0.1

Type RM Length L Ch R = 1,372,0,0,0
BEGIN DESCRIPTION:
SILVERMINE CREEK 1.0
END DESCRIPTION:
XS GIS Cut Line= 3
      2782998.26     10170407.48      2782677.10     10169878.00
      2782500.38     10169890.13
#Sta/Elev= 30
  4586.6 1285.54  4591.3 1285.54  4647.4 1283.47  4738.7 1283.46  4810.7 1281.74
  4832.0 1282.41  4847.5 1281.19  4868.9 1276.91  4874.7 1273.96  4896.0 1271.20
  4919.2 1272.75  4927.0 1271.45  4932.9 1272.25  4963.8 1267.53  4995.6 1266.74
  4996.1 1263.74  5005.3 1263.74  5005.8 1266.74  5036.2 1267.80  5064.7 1271.19
  5086.0 1270.33  5117.0 1271.86  5122.8 1273.51  5129.7 1272.83  5138.3 1273.91
  5159.7 1278.99  5205.8 1281.93  5327.6 1283.33  5358.1 1282.61  5383.0 1284.89
#Mann=6,-1,0
  4586.6    0.12       0  4591.3    0.05       0  4647.4    0.12       0
  4738.7    0.05       0  4995.6    0.03       0  5005.8    0.05       0
Bank Sta=4995.6,5005.8
Exp/Cntr=0.3,0.1

Chan Stop Cuts=-1