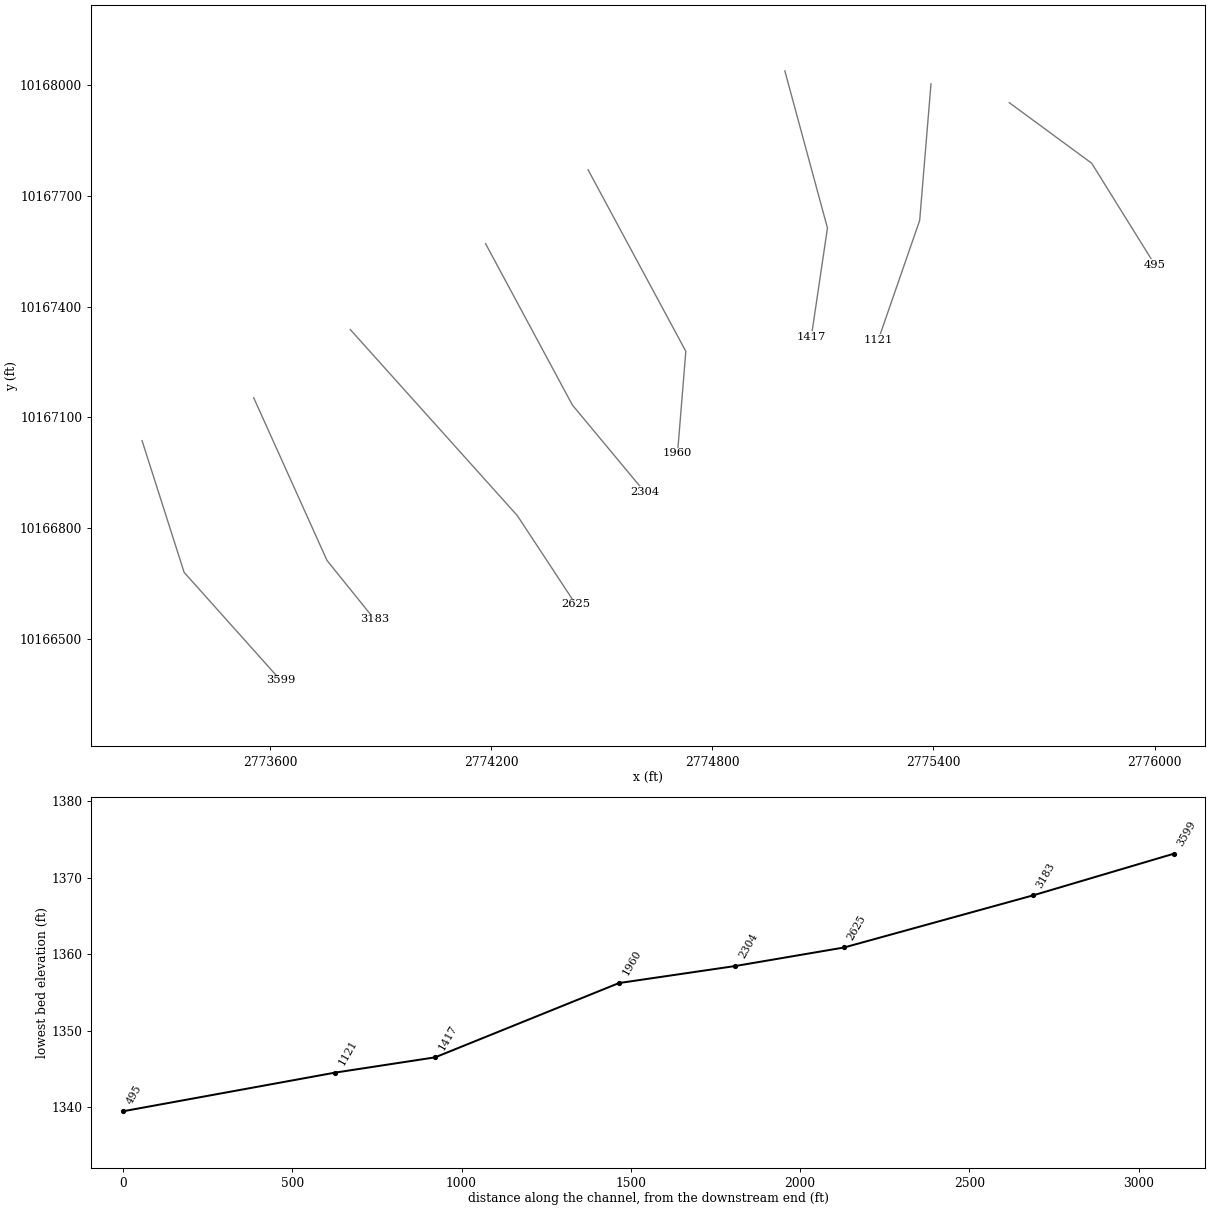
HEC-RAS study SOUTH HELMS CREEK.prj: SOUTH HELMS CREEK Base Level Engineering

--- SOUTH HELMS CREEK.g01 (geometry) --- (continued)

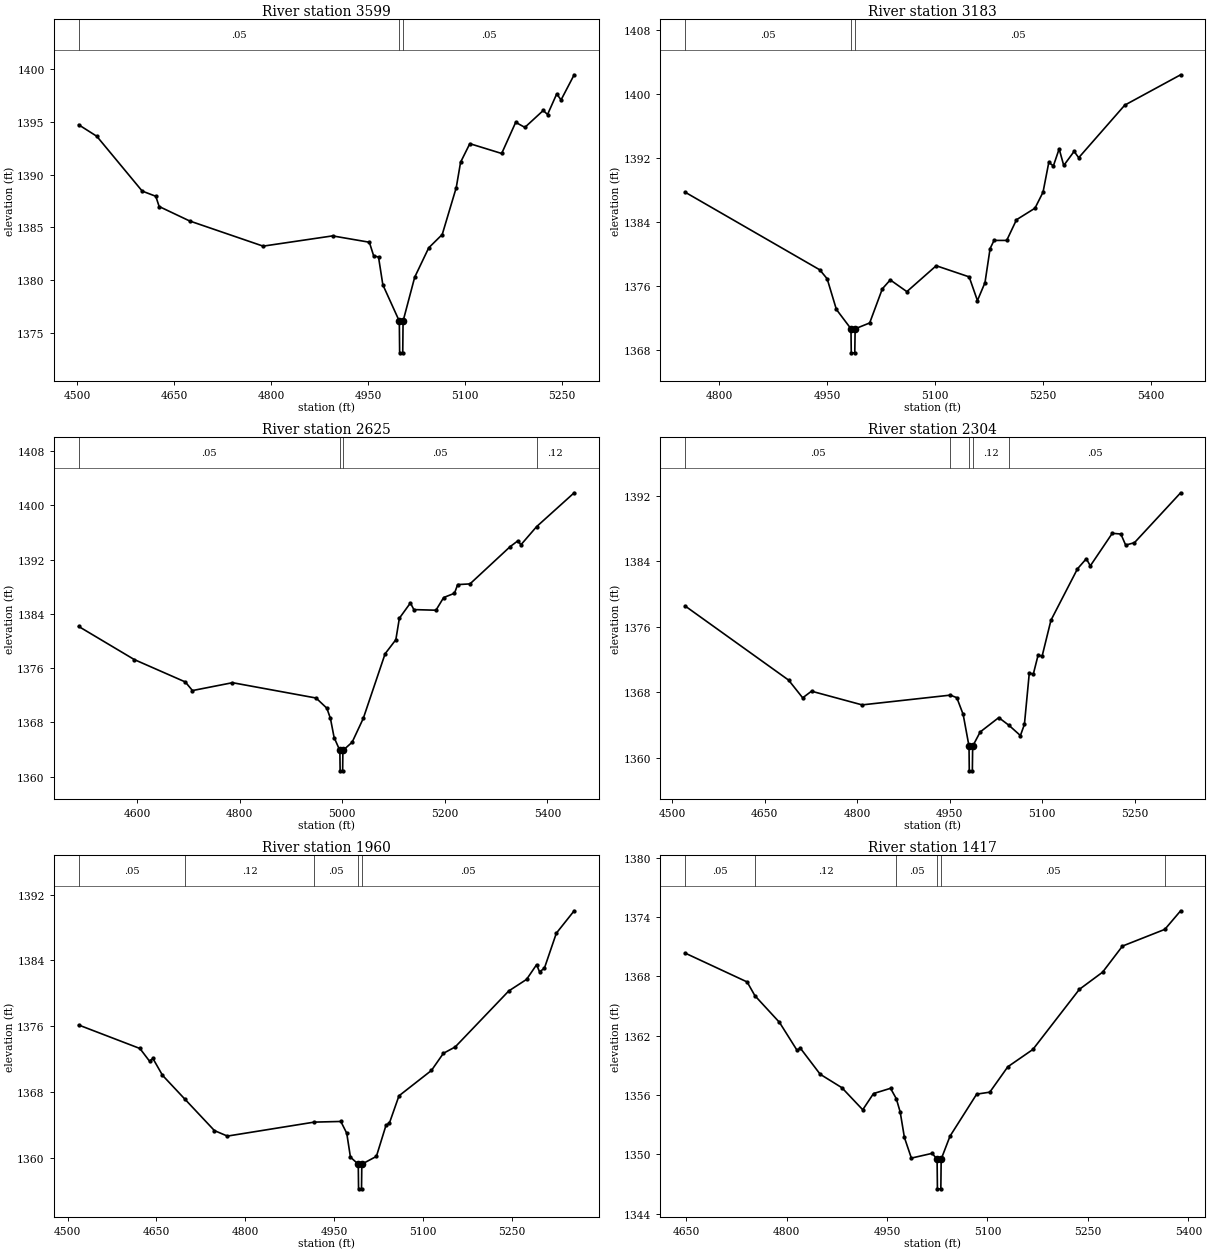
Type RM Length L Ch R = 1,3599,416,416,416
BEGIN DESCRIPTION:
SOUTH HELMS CREEK 7.0
END DESCRIPTION:
XS GIS Cut Line= 3
      2773252.75     10167036.84      2773366.89     10166679.79
      2773628.35     10166387.66
#Sta/Elev= 30
  4501.9 1394.71  4530.0 1393.62  4600.3 1388.43  4621.3 1387.94  4626.5 1386.97
  4673.8 1385.60  4787.4 1383.22  4894.9 1384.19  4951.8 1383.59  4958.5 1382.30
  4966.0 1382.19  4972.7 1379.56  4998.2 1376.12  4998.7 1373.12  5003.5 1373.12
  5004.0 1376.12  5022.0 1380.28  5043.7 1383.06  5064.6 1384.32  5086.3 1388.76
  5093.0 1391.16  5107.3 1392.92  5156.6 1391.99  5178.3 1394.94  5192.5 1394.46
  5220.9 1396.06  5227.6 1395.68  5241.8 1397.63  5248.5 1397.06  5268.8 1399.44
#Mann=3,-1,0
  4501.9    0.05       0  4998.2    0.05       0  5004.0    0.05       0
Bank Sta=4998.2,5004
Exp/Cntr=0.3,0.1

Type RM Length L Ch R = 1,3183,558,558,558
BEGIN DESCRIPTION:
SOUTH HELMS CREEK 6.0
END DESCRIPTION:
XS GIS Cut Line= 3
      2773555.68     10167153.11      2773754.63     10166711.98
      2773883.39     10166552.49
#Sta/Elev= 30
  4752.8 1387.72  4940.0 1378.03  4950.3 1376.91  4963.1 1373.09  4983.4 1370.67
  4983.8 1367.67  4988.7 1367.67  4989.2 1370.67  5009.4 1371.40  5027.0 1375.66
  5038.0 1376.77  5061.1 1375.31  5101.9 1378.54  5147.7 1377.15  5159.2 1374.19
  5169.7 1376.43  5176.8 1380.68  5182.3 1381.70  5199.9 1381.70  5213.5 1384.28
  5239.2 1385.72  5250.4 1387.72  5258.4 1391.43  5264.8 1391.00  5272.8 1393.12
  5279.2 1391.05  5293.6 1392.81  5300.0 1392.02  5364.0 1398.58  5441.7 1402.37
#Mann=3,-1,0
  4752.8    0.05       0  4983.4    0.05       0  4989.2    0.05       0
Bank Sta=4983.4,4989.2
Exp/Cntr=0.3,0.1

Type RM Length L Ch R = 1,2625,321,321,321
BEGIN DESCRIPTION:
SOUTH HELMS CREEK 5.0
END DESCRIPTION:
XS GIS Cut Line= 3
      2773817.57     10167338.18      2774271.12     10166833.42
      2774429.14     10166593.47
#Sta/Elev= 30
  4486.1 1382.16  4594.6 1377.27  4694.0 1373.97  4708.0 1372.70  4786.0 1373.86
  4948.9 1371.60  4969.9 1370.10  4976.9 1368.59  4984.1 1365.77  4995.3 1363.86
  4995.8 1360.86  5000.7 1360.86  5001.2 1363.86  5019.2 1365.08  5040.9 1368.59
  5083.5 1378.13  5104.4 1380.20  5111.3 1383.37  5132.8 1385.62  5139.5 1384.64
  5182.6 1384.55  5197.6 1386.42  5218.7 1387.05  5224.9 1388.33  5248.9 1388.43
  5327.1 1393.92  5342.2 1394.78  5348.2 1394.20  5378.7 1396.87  5452.0 1401.87
#Mann=4,-1,0
  4486.1    0.05       0  4995.3    0.05       0  5001.2    0.05       0
  5378.7    0.12       0
Bank Sta=4995.3,5001.2
Exp/Cntr=0.3,0.1

Type RM Length L Ch R = 1,2304,344,344,344
BEGIN DESCRIPTION:
Mapping XS 0ed5a3d6
END DESCRIPTION:
XS GIS Cut Line= 3
      2774184.78     10167570.89      2774420.37     10167133.37
      2774616.30     10166897.95
#Sta/Elev= 30
  4521.2 1378.54  4689.0 1369.50  4711.8 1367.34  4726.1 1368.15  4808.1 1366.48
  4951.1 1367.67  4961.6 1367.36  4971.9 1365.32  4981.4 1361.44  4981.8 1358.44
  4986.8 1358.44  4987.3 1361.44  4999.5 1363.18  5029.6 1364.93  5046.3 1363.98
  5064.7 1362.74  5071.2 1364.11  5079.1 1370.37  5085.6 1370.23  5093.4 1372.56
  5099.9 1372.43  5114.2 1376.80  5157.2 1383.07  5171.5 1384.30  5178.0 1383.43
  5213.6 1387.40  5227.5 1387.31  5235.3 1385.96  5249.6 1386.26  5324.4 1392.34
#Mann=5,-1,0
  4521.2    0.05       0  4951.1    0.12       0  4981.4    0.07       0
  4987.3    0.12       0  5046.3    0.05       0
Bank Sta=4981.4,4987.3
Exp/Cntr=0.3,0.1

Type RM Length L Ch R = 1,1960,543,543,543
BEGIN DESCRIPTION:
SOUTH HELMS CREEK 4.0
END DESCRIPTION:
XS GIS Cut Line= 3
      2774462.80     10167771.31      2774728.18     10167279.01
      2774705.68     10167003.10
#Sta/Elev= 30
  4518.7 1376.15  4622.1 1373.29  4638.3 1371.75  4644.0 1372.08  4660.2 1370.03
  4697.9 1367.13  4747.8 1363.30  4769.7 1362.63  4916.2 1364.33  4961.1 1364.41
  4971.1 1362.97  4977.3 1360.07  4990.5 1359.21  4991.0 1356.21  4996.0 1356.21
  4996.5 1359.21  5021.1 1360.16  5037.3 1363.94  5043.0 1364.20  5059.2 1367.53
  5114.0 1370.62  5134.1 1372.70  5154.1 1373.48  5244.4 1380.29  5274.5 1381.70
  5291.4 1383.49  5296.4 1382.61  5304.6 1383.07  5324.7 1387.32  5354.8 1390.05
#Mann=5,-1,0
  4518.7    0.05       0  4697.9    0.12       0  4916.2    0.05       0
  4990.5    0.05       0  4996.5    0.05       0
Bank Sta=4990.5,4996.5
Exp/Cntr=0.3,0.1

Type RM Length L Ch R = 1,1417,296,296,296
BEGIN DESCRIPTION:
SOUTH HELMS CREEK 3.0
END DESCRIPTION:
XS GIS Cut Line= 3
      2774996.85     10168039.07      2775112.44     10167613.29
      2775068.58     10167317.92
#Sta/Elev= 30
  4648.6 1370.35  4741.2 1367.43  4752.8 1366.04  4789.5 1363.34  4815.6 1360.53
  4820.8 1360.72  4850.3 1358.09  4882.7 1356.73  4913.8 1354.50  4929.9 1356.14
  4955.3 1356.67  4963.9 1355.62  4969.7 1354.28  4976.0 1351.70  4986.4 1349.61
  5017.4 1350.09  5024.8 1349.50  5025.3 1346.50  5030.4 1346.50  5030.9 1349.50
  5044.1 1351.83  5083.9 1356.08  5103.5 1356.28  5130.4 1358.85  5167.8 1360.60
  5237.2 1366.68  5271.9 1368.42  5301.6 1371.06  5364.8 1372.75  5388.4 1374.63
#Mann=6,-1,0
  4648.6    0.05       0  4752.8    0.12       0  4963.9    0.05       0
  5024.8    0.03       0  5030.9    0.05       0  5364.8    0.12       0
Bank Sta=5024.8,5030.9
Exp/Cntr=0.3,0.1

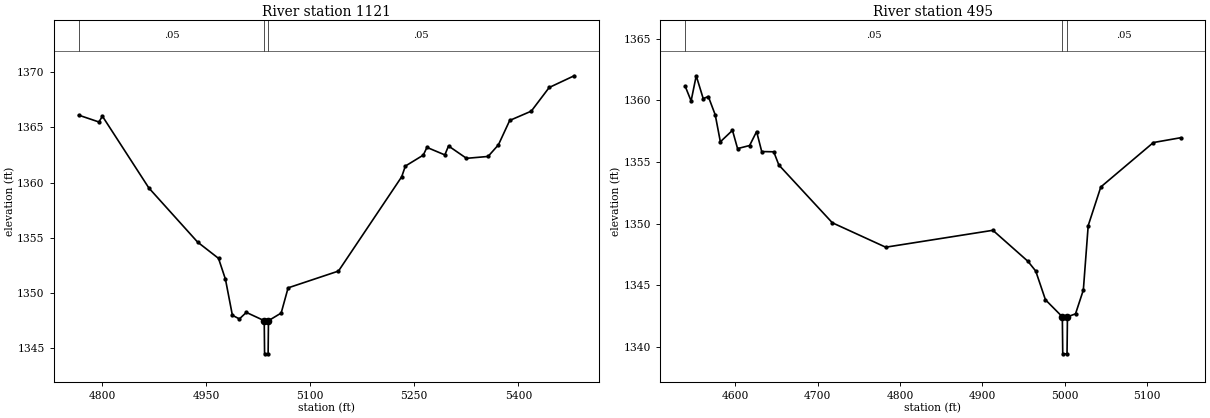
Type RM Length L Ch R = 1,1121,626,626,626
BEGIN DESCRIPTION:
SOUTH HELMS CREEK 2.0
END DESCRIPTION:
XS GIS Cut Line= 3
      2775393.37     10168003.98      2775362.65     10167633.77
      2775250.34     10167309.97
#Sta/Elev= 30
  4766.2 1366.10  4795.4 1365.48  4800.5 1366.00  4867.4 1359.51  4937.7 1354.61
  4967.8 1353.14  4977.8 1351.25  4987.8 1347.99  4997.9 1347.66  5007.9 1348.25
  5033.7 1347.50  5034.2 1344.50  5039.3 1344.50  5039.8 1347.50  5058.1 1348.19
  5068.1 1350.47  5140.7 1351.99  5231.8 1360.52  5237.1 1361.49  5262.9 1362.48
  5268.2 1363.18  5294.0 1362.50  5299.3 1363.31  5325.2 1362.19  5356.3 1362.36
  5371.2 1363.41  5387.5 1365.62  5418.6 1366.46  5444.4 1368.60  5480.4 1369.66
#Mann=3,-1,0
  4766.2    0.05       0  5033.7    0.03       0  5039.8    0.05       0
Bank Sta=5033.7,5039.8
Exp/Cntr=0.3,0.1

Type RM Length L Ch R = 1,495,0,0,0
BEGIN DESCRIPTION:
SOUTH HELMS CREEK 1.0
END DESCRIPTION:
XS GIS Cut Line= 3
      2775605.68     10167953.11      2775829.40     10167788.87
      2776000.57     10167513.82
#Sta/Elev= 30
  4539.2 1361.15  4546.5 1359.94  4552.7 1361.98  4561.2 1360.13  4567.4 1360.30
  4575.8 1358.81  4582.0 1356.63  4596.7 1357.56  4602.9 1356.08  4617.5 1356.33
  4626.0 1357.46  4632.2 1355.84  4646.8 1355.82  4653.0 1354.75  4717.9 1350.07
  4782.7 1348.09  4912.8 1349.46  4955.3 1346.95  4964.8 1346.16  4976.6 1343.83
  4997.1 1342.45  4997.6 1339.45  5002.8 1339.45  5003.3 1342.45  5013.1 1342.69
  5022.6 1344.62  5028.5 1349.84  5043.8 1352.97  5107.6 1356.57  5140.7 1356.96
#Mann=3,-1,0
  4539.2    0.05       0  4997.1    0.05       0  5003.3    0.05       0
Bank Sta=4997.1,5003.3
Exp/Cntr=0.3,0.1

Chan Stop Cuts=-1