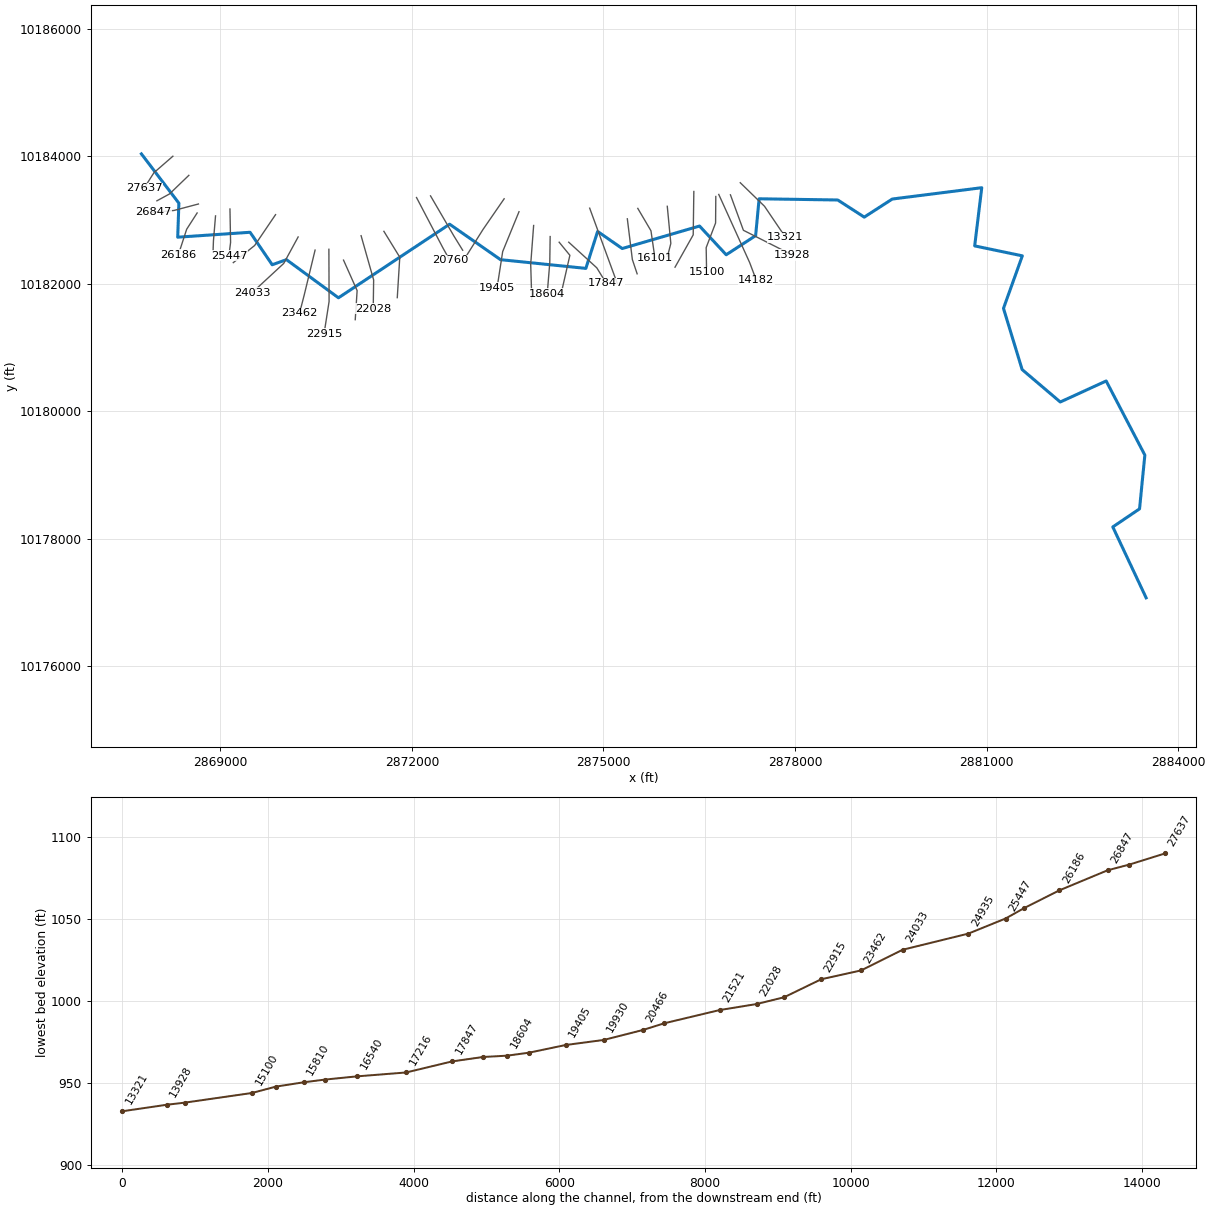
--- UPSHAW CREEK.prj (project) ---

Proj Title=UPSHAW CREEK Base Level Engineering
Current Plan=p01
Default Exp/Contr=0.3,0.1
English Units
Geom File=g01
Flow File=f01
Plan File=p01
BEGIN DESCRIPTION:
UPSHAW CREEK
END DESCRIPTION:

--- UPSHAW CREEK.p01 (plan) ---

Plan Title=Multiple Run
Short Identifier=Multiple
Geom File=g01
Flow File=f01
Subcritical Flow
K Sum by GR= 0
Std Step Tol= 0.01
Critical Tol= 0.01
Num of Std Step Trials= 20
Max Error Tol= 0.3
Flow Tol Ratio= 0.001
Split Flow NTrial= 30
Split Flow Tol= 0.02
Split Flow Ratio= 0.02
Log Output Level= 0
Friction Slope Method= 1
Unsteady Friction Slope Method= 2
Unsteady Bridges Friction Slope Method= 1
Parabolic Critical Depth
Global Vel Dist=  1 , 1 , 1
Global Log Level= 0
CheckData=True
Encroach Param= -1, 0, 0, 0
BEGIN DESCRIPTION:
Multiple Run
END DESCRIPTION:

--- UPSHAW CREEK.f01 (steady flow) ---

Flow Title=Multiple
Number of Profiles=7
Profile Names=10-year,25-year,50-year,1pct_min,100-year,1pct_plu,500-year
River Rch & RM= UPSHAW CREEK,Reach-1,27637
      70     134     210     109     329     995     870
River Rch & RM= UPSHAW CREEK,Reach-1,18903
     111     229     369     196     593    1791    1634
River Rch & RM= UPSHAW CREEK,Reach-1,15100
     125     260     423     226     683    2062    1900
River Rch & RM= UPSHAW CREEK,Reach-1,10580
     157     335     550     297     897    2710    2540
River Rch & RM= UPSHAW CREEK,Reach-1,9495
     188     410     680     370    1116    3371    3199
River Rch & RM= UPSHAW CREEK,Reach-1,4785
     202     441     733     400    1207    3646    3476
River Rch & RM= UPSHAW CREEK,Reach-1,1280
     248     553     926     508    1534    4633    4475
Boundary for River Rch & Prof#=UPSHAW CREEK,Reach-1,1
Up Type=0
Dn Type=3
Dn Slope=0.005
Boundary for River Rch & Prof#=UPSHAW CREEK,Reach-1,2
Up Type=0
Dn Type=3
Dn Slope=0.005
Boundary for River Rch & Prof#=UPSHAW CREEK,Reach-1,3
Up Type=0
Dn Type=3
Dn Slope=0.005
Boundary for River Rch & Prof#=UPSHAW CREEK,Reach-1,4
Up Type=0
Dn Type=3
Dn Slope=0.005
Boundary for River Rch & Prof#=UPSHAW CREEK,Reach-1,5
Up Type=0
Dn Type=3
Dn Slope=0.005
Boundary for River Rch & Prof#=UPSHAW CREEK,Reach-1,6
Up Type=0
Dn Type=3
Dn Slope=0.005
Boundary for River Rch & Prof#=UPSHAW CREEK,Reach-1,7
Up Type=0
Dn Type=3
Dn Slope=0.005

--- UPSHAW CREEK.g01 (geometry) ---

Geom Title=Existing Conditions

River Reach=UPSHAW CREEK,Reach-1
Reach XY= 30
      2867762.75     10184040.00      2868349.75     10183266.00
      2868331.50     10182732.00      2869465.00     10182809.00
      2869811.50     10182299.00      2870034.75     10182379.00
      2870849.00     10181780.00      2872590.00     10182936.00
      2873387.50     10182379.00      2874724.00     10182242.00
      2874908.25     10182822.00      2875293.50     10182554.00
      2876504.25     10182907.00      2876922.00     10182456.00
      2877382.75     10182756.00      2877437.50     10183335.00
      2878669.25     10183316.00      2879084.25     10183047.00
      2879523.00     10183331.00      2880924.50     10183509.00
      2880813.75     10182595.00      2881560.00     10182439.00
      2881264.75     10181614.00      2881557.00     10180653.00
      2882154.50     10180144.00      2882873.25     10180474.00
      2883479.00     10179310.00      2883395.75     10178466.00
      2882977.00     10178182.00      2883499.25     10177069.00

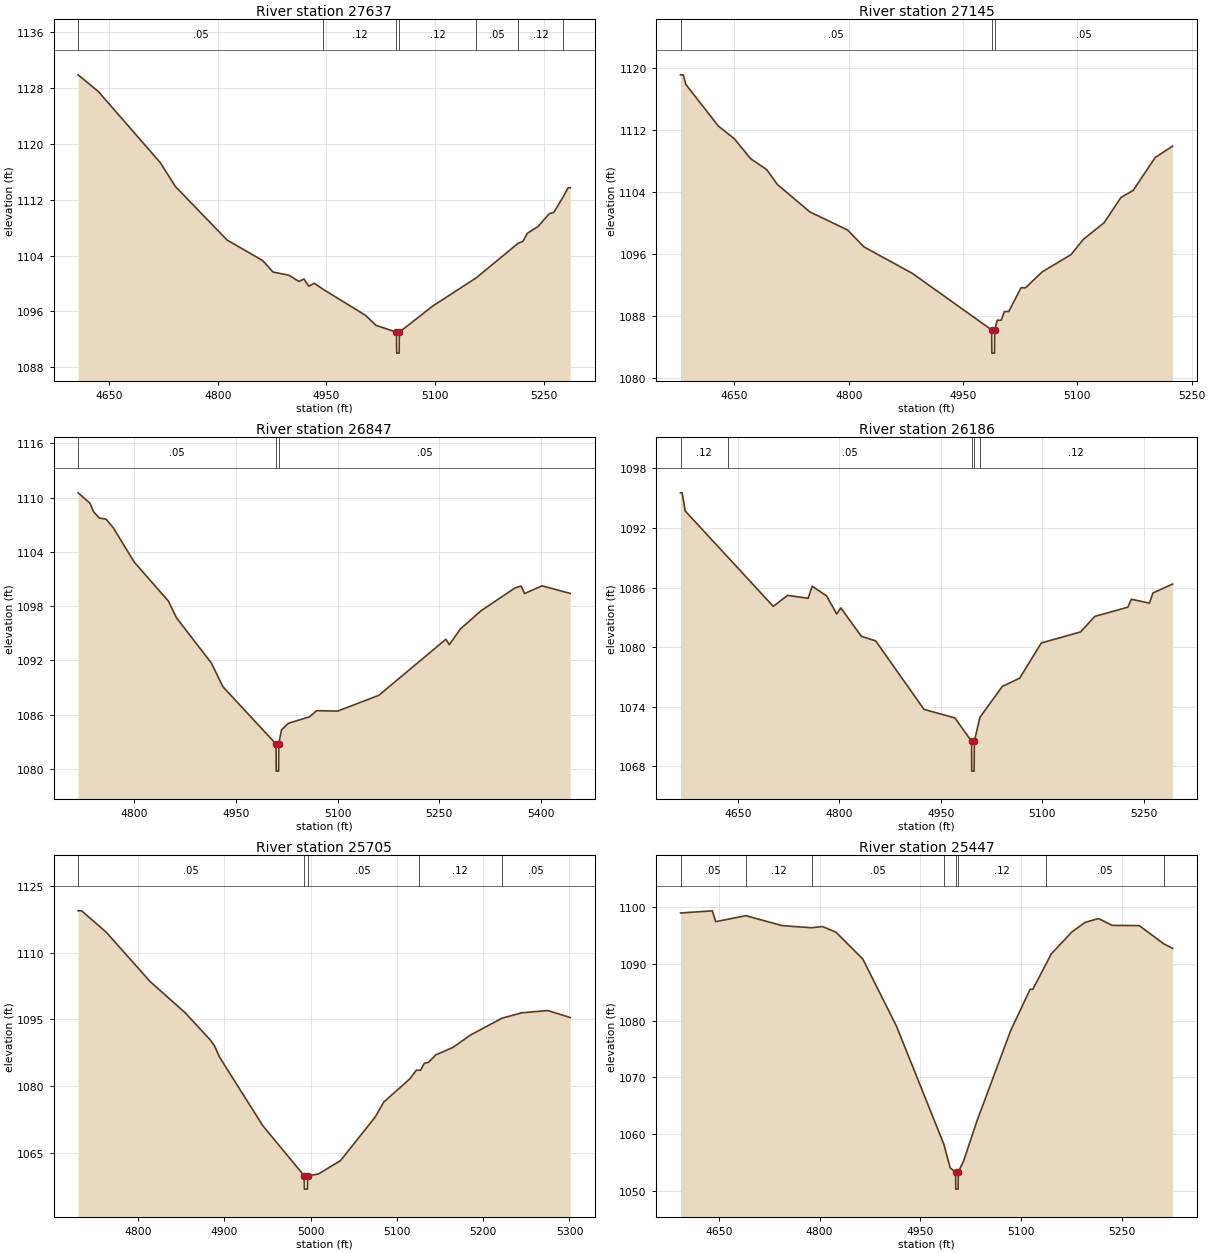
Type RM Length L Ch R = 1,27637,492,492,492
BEGIN DESCRIPTION:
UPSHAW CREEK 55.0
END DESCRIPTION:
XS GIS Cut Line= 3
      2868255.71     10184003.13      2867959.50     10183745.00
      2867805.66     10183503.07
#Sta/Elev= 30
  4607.1 1129.86  4635.1 1127.46  4720.6 1117.29  4741.5 1113.87  4812.7 1106.23
  4862.0 1103.28  4876.3 1101.64  4898.1 1101.19  4912.2 1100.29  4919.0 1100.65
  4925.6 1099.61  4933.2 1100.04  4945.7 1099.16  5004.1 1095.44  5018.2 1094.02
  5046.7 1093.04  5047.0 1090.04  5050.5 1090.04  5050.7 1093.04  5097.0 1096.79
  5157.0 1100.82  5214.9 1105.77  5221.4 1106.04  5227.4 1107.18  5242.6 1108.19
  5257.9 1110.01  5263.8 1110.16  5276.8 1112.37  5283.7 1113.70  5286.7 1113.70
#Mann=7,-1,0
  4607.1    0.05       0  4945.7    0.12       0  5046.7    0.07       0
  5050.7    0.12       0  5157.0    0.05       0  5214.9    0.12       0
  5276.8    0.05       0
Bank Sta=5046.7,5050.7
Exp/Cntr=0.3,0.1

Type RM Length L Ch R = 1,27145,298,298,298
BEGIN DESCRIPTION:
UPSHAW CREEK 54.0
END DESCRIPTION:
XS GIS Cut Line= 3
      2868505.72     10183703.15      2868203.00     10183411.00
      2868005.67     10183303.10
#Sta/Elev= 30
  4579.3 1119.16  4582.8 1119.16  4586.4 1117.91  4628.9 1112.55  4650.0 1110.90
  4671.3 1108.33  4692.4 1106.92  4706.6 1104.98  4749.0 1101.46  4798.7 1099.11
  4819.8 1096.95  4883.5 1093.52  4987.5 1086.22  4987.8 1083.22  4991.3 1083.22
  4991.5 1086.22  4994.9 1087.47  5000.0 1087.47  5004.3 1088.58  5010.0 1088.60
  5026.1 1091.67  5031.8 1091.65  5053.9 1093.72  5091.6 1095.94  5107.7 1097.90
  5135.2 1100.07  5157.1 1103.32  5173.2 1104.23  5202.1 1108.49  5224.9 1109.95
#Mann=3,-1,0
  4579.3    0.05       0  4987.5    0.03       0  4991.5    0.05       0
Bank Sta=4987.5,4991.5
Exp/Cntr=0.3,0.1

Type RM Length L Ch R = 1,26847,661,661,661
BEGIN DESCRIPTION:
UPSHAW CREEK 53.0
END DESCRIPTION:
XS GIS Cut Line= 3
      2868655.71     10183253.12      2868271.91     10183151.48
      2867944.37     10183122.00
#Sta/Elev= 30
  4717.2 1110.53  4734.8 1109.37  4739.9 1108.44  4748.3 1107.75  4758.6 1107.60
  4769.0 1106.67  4800.0 1102.86  4850.2 1098.57  4862.1 1096.72  4913.8 1091.69
  4930.7 1089.08  5009.1 1082.74  5009.4 1079.74  5012.9 1079.74  5013.1 1082.74
  5017.2 1084.31  5027.6 1085.04  5058.6 1085.75  5069.0 1086.43  5100.0 1086.38
  5160.6 1088.12  5259.7 1094.33  5264.7 1093.73  5281.1 1095.47  5311.3 1097.47
  5361.5 1100.00  5370.7 1100.21  5375.7 1099.39  5401.6 1100.24  5443.1 1099.40
#Mann=3,-1,0
  4717.2    0.05       0  5009.1    0.03       0  5013.1    0.05       0
Bank Sta=5009.1,5013.1
Exp/Cntr=0.3,0.1

Type RM Length L Ch R = 1,26186,481,481,481
BEGIN DESCRIPTION:
UPSHAW CREEK 52.0
END DESCRIPTION:
XS GIS Cut Line= 3
      2868635.51     10183112.18      2868471.64     10182856.51
      2868340.69     10182453.74
#Sta/Elev= 30
  4565.3 1095.54  4567.7 1095.54  4572.2 1093.72  4634.8 1089.10  4702.4 1084.11
  4723.5 1085.22  4753.9 1084.93  4759.9 1086.14  4781.0 1085.18  4796.2 1083.35
  4802.2 1083.96  4832.6 1081.10  4853.7 1080.64  4925.1 1073.75  4970.8 1072.88
  4995.5 1070.53  4995.7 1067.53  4999.2 1067.53  4999.5 1070.53  5007.8 1072.95
  5040.8 1076.05  5066.6 1076.89  5098.5 1080.43  5156.5 1081.54  5177.5 1083.10
  5226.3 1084.03  5231.6 1084.83  5258.3 1084.44  5263.5 1085.46  5292.5 1086.36
#Mann=5,-1,0
  4565.3    0.12       0  4634.8    0.05       0  4995.5    0.03       0
  4999.5    0.05       0  5007.8    0.12       0
Bank Sta=4995.5,4999.5
Exp/Cntr=0.3,0.1

Type RM Length L Ch R = 1,25705,258,258,258
BEGIN DESCRIPTION:
UPSHAW CREEK 51.0
END DESCRIPTION:
XS GIS Cut Line= 3
      2868923.75     10183066.30      2868891.00     10182673.24
      2868884.48     10182497.28
#Sta/Elev= 30
  4730.4 1119.45  4734.5 1119.45  4763.0 1114.63  4813.9 1103.51  4854.0 1096.59
  4883.4 1090.42  4888.5 1089.05  4894.1 1086.59  4944.3 1071.12  4992.5 1059.79
  4992.7 1056.79  4996.2 1056.79  4996.5 1059.79  5008.9 1060.19  5034.6 1063.21
  5074.8 1073.03  5084.8 1076.41  5114.9 1081.61  5122.4 1083.56  5125.0 1083.56
  5127.4 1083.56  5131.7 1085.11  5136.7 1085.35  5145.0 1087.01  5165.0 1088.71
  5185.0 1091.45  5221.8 1095.28  5245.0 1096.50  5275.0 1097.00  5300.9 1095.43
#Mann=5,-1,0
  4730.4    0.05       0  4992.5    0.05       0  4996.5    0.05       0
  5125.0    0.12       0  5221.8    0.05       0
Bank Sta=4992.5,4996.5
Exp/Cntr=0.3,0.1

Type RM Length L Ch R = 1,25447,512,512,512
BEGIN DESCRIPTION:
UPSHAW CREEK 50.0
END DESCRIPTION:
XS GIS Cut Line= 3
      2869149.77     10183174.37      2869159.60     10182650.31
      2869133.39     10182443.92
#Sta/Elev= 30
  4593.1 1098.92  4640.5 1099.30  4645.5 1097.39  4690.2 1098.45  4744.4 1096.70
  4788.4 1096.32  4804.4 1096.54  4824.4 1095.55  4864.4 1090.82  4914.4 1079.03
  4984.9 1058.26  4994.4 1054.08  5002.4 1053.35  5002.7 1050.35  5006.2 1050.35
  5006.4 1053.35  5014.4 1055.31  5034.4 1062.40  5084.4 1078.24  5113.4 1085.50
  5117.3 1085.50  5137.5 1090.06  5144.7 1091.71  5174.9 1095.52  5195.1 1097.27
  5215.2 1097.94  5235.4 1096.74  5275.7 1096.70  5311.9 1093.52  5325.3 1092.70
#Mann=8,-1,0
  4593.1    0.05       0  4690.2    0.12       0  4788.4    0.05       0
  4984.9    0.12       0  5002.4    0.07       0  5006.4    0.12       0
  5137.5    0.05       0  5311.9    0.12       0
Bank Sta=5002.4,5006.4
Exp/Cntr=0.3,0.1

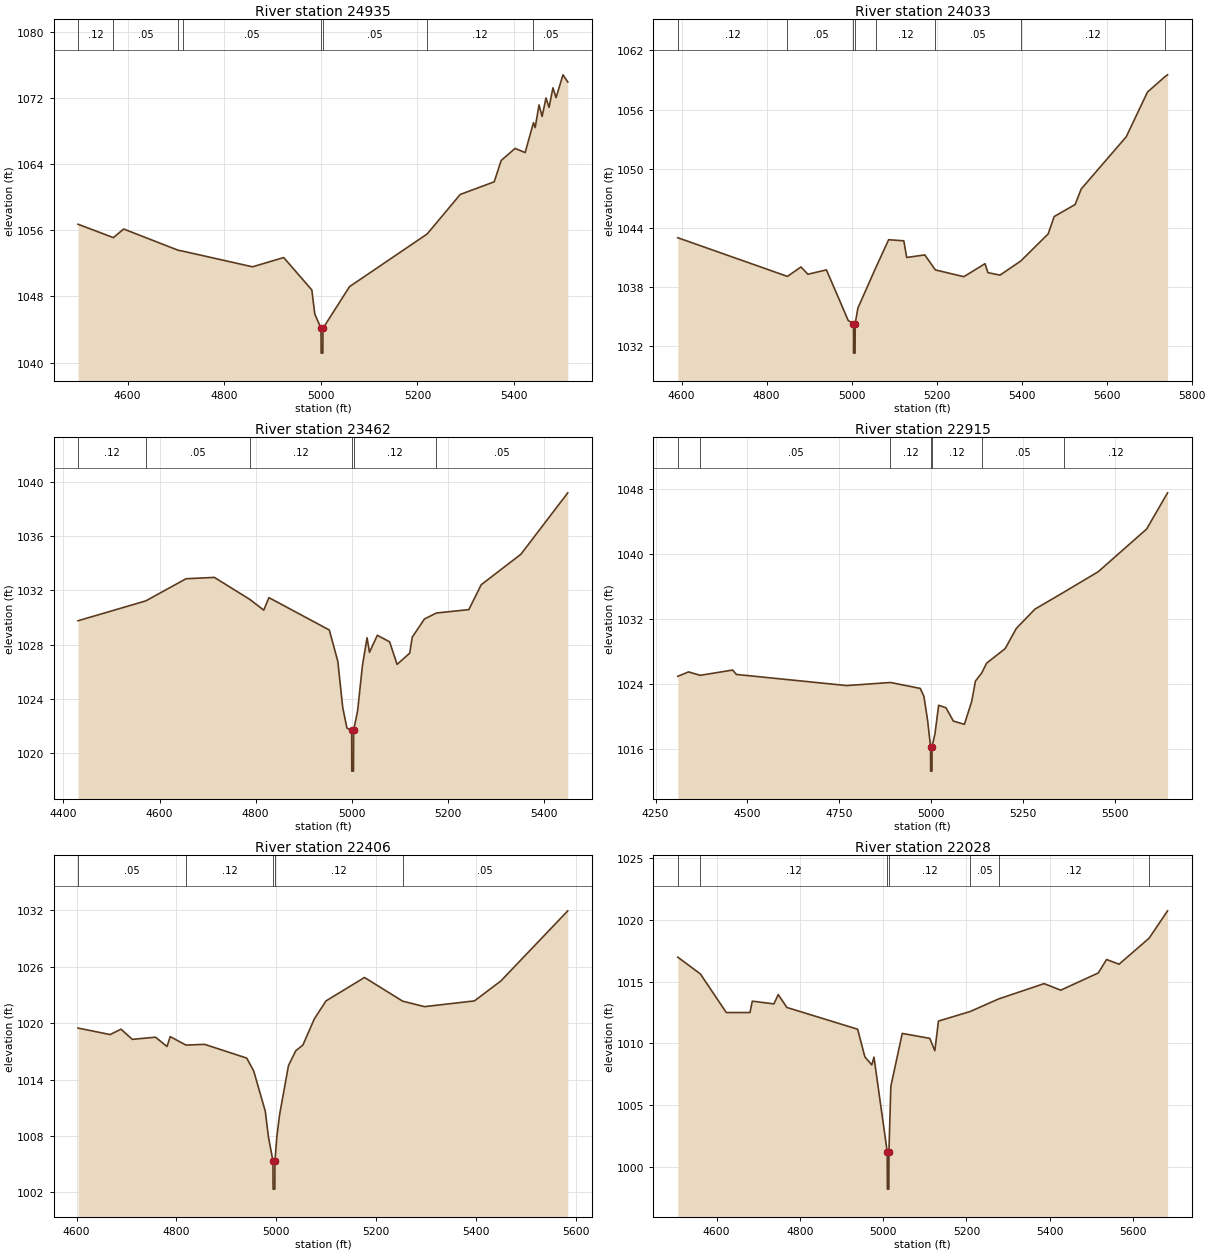
Type RM Length L Ch R = 1,24935,902,902,902
BEGIN DESCRIPTION:
UPSHAW CREEK 49.0
END DESCRIPTION:
XS GIS Cut Line= 3
      2869863.85     10183085.95      2869536.30     10182601.18
      2869202.15     10182332.55
#Sta/Elev= 30
  4497.4 1056.73  4570.6 1055.11  4591.9 1056.15  4704.4 1053.59  4714.6 1053.47
  4858.6 1051.58  4923.2 1052.70  4981.4 1048.78  4987.5 1045.87  5000.4 1044.14
  5000.7 1041.14  5004.2 1041.14  5004.4 1044.14  5059.4 1049.18  5220.1 1055.55
  5288.5 1060.33  5358.9 1061.86  5373.3 1064.44  5402.1 1065.90  5422.9 1065.40
  5440.2 1069.01  5443.7 1068.42  5451.7 1071.16  5458.1 1069.77  5466.1 1072.00
  5472.5 1070.87  5480.5 1073.23  5486.9 1072.04  5501.3 1074.80  5511.2 1073.93
#Mann=8,-1,0
  4497.4    0.12       0  4570.6    0.05       0  4704.4    0.12       0
  4714.6    0.05       0  5000.4    0.03       0  5004.4    0.05       0
  5220.1    0.12       0  5440.2    0.05       0
Bank Sta=5000.4,5004.4
Exp/Cntr=0.3,0.1

Type RM Length L Ch R = 1,24033,571,571,571
BEGIN DESCRIPTION:
UPSHAW CREEK 48.0
END DESCRIPTION:
XS GIS Cut Line= 3
      2870217.61     10182735.45      2869991.61     10182319.47
      2869493.96     10181857.84
#Sta/Elev= 30
  4591.1 1043.00  4849.0 1039.08  4880.9 1040.04  4897.1 1039.30  4940.8 1039.74
  4992.1 1034.60  5004.4 1034.30  5004.6 1031.30  5008.1 1031.30  5008.4 1034.30
  5014.8 1035.87  5056.5 1039.93  5087.1 1042.80  5122.8 1042.69  5129.6 1041.00
  5172.2 1041.26  5197.0 1039.74  5264.0 1039.05  5313.9 1040.37  5320.7 1039.46
  5349.1 1039.21  5397.9 1040.64  5462.4 1043.39  5476.6 1045.15  5525.9 1046.37
  5540.1 1047.94  5646.1 1053.24  5696.0 1057.77  5737.1 1059.33  5743.3 1059.52
#Mann=8,-1,0
  4591.1    0.12       0  4849.0    0.05       0  5004.4    0.05       0
  5008.4    0.05       0  5056.5    0.12       0  5197.0    0.05       0
  5397.9    0.12       0  5737.1    0.05       0
Bank Sta=5004.4,5008.4
Exp/Cntr=0.3,0.1

Type RM Length L Ch R = 1,23462,547,547,547
BEGIN DESCRIPTION:
UPSHAW CREEK 47.0
END DESCRIPTION:
XS GIS Cut Line= 3
      2870482.95     10182529.11      2870313.56     10181827.35
      2870239.50     10181538.51
#Sta/Elev= 30
  4430.3 1029.76  4571.3 1031.22  4655.3 1032.85  4714.2 1032.95  4788.2 1031.33
  4817.1 1030.54  4828.0 1031.46  4953.7 1029.08  4971.4 1026.78  4981.7 1023.37
  4990.4 1021.87  5000.3 1021.70  5000.5 1018.70  5004.0 1018.70  5004.3 1021.70
  5012.6 1023.13  5022.8 1026.50  5032.3 1028.51  5037.4 1027.44  5053.7 1028.69
  5079.3 1028.21  5094.9 1026.55  5121.2 1027.38  5126.4 1028.55  5151.8 1029.89
  5176.7 1030.33  5244.3 1030.58  5270.1 1032.41  5352.7 1034.65  5450.4 1039.17
#Mann=6,-1,0
  4430.3    0.12       0  4571.3    0.05       0  4788.2    0.12       0
  5000.3    0.07       0  5004.3    0.12       0  5176.7    0.05       0
Bank Sta=5000.3,5004.3
Exp/Cntr=0.3,0.1

Type RM Length L Ch R = 1,22915,509,509,509
BEGIN DESCRIPTION:
UPSHAW CREEK 46.0
END DESCRIPTION:
XS GIS Cut Line= 3
      2870699.14     10182542.24      2870702.42     10181723.31
      2870624.00     10181216.88
#Sta/Elev= 30
  4310.6 1024.98  4339.7 1025.52  4371.6 1025.10  4459.7 1025.75  4469.7 1025.21
  4769.7 1023.84  4888.7 1024.22  4969.7 1023.49  4979.7 1022.51  4989.7 1019.55
  4997.7 1016.32  4998.0 1013.32  5001.5 1013.32  5001.7 1016.32  5009.7 1017.91
  5019.7 1021.42  5039.7 1021.11  5059.7 1019.47  5089.7 1019.08  5109.7 1021.91
  5119.7 1024.39  5136.8 1025.39  5150.0 1026.59  5200.6 1028.39  5230.9 1030.87
  5281.5 1033.24  5360.8 1035.34  5453.5 1037.84  5585.1 1043.09  5642.0 1047.54
#Mann=7,-1,0
  4310.6    0.12       0  4371.6    0.05       0  4888.7    0.12       0
  4997.7    0.07       0  5001.7    0.12       0  5136.8    0.05       0
  5360.8    0.12       0
Bank Sta=4997.7,5001.7
Exp/Cntr=0.3,0.1

Type RM Length L Ch R = 1,22406,378,378,378
BEGIN DESCRIPTION:
UPSHAW CREEK 45.0
END DESCRIPTION:
XS GIS Cut Line= 3
      2870928.45     10182371.85      2871141.35     10181893.64
      2871111.96     10181436.54
#Sta/Elev= 30
  4602.9 1019.48  4667.2 1018.79  4689.1 1019.36  4711.6 1018.28  4758.1 1018.51
  4781.3 1017.52  4787.6 1018.57  4819.3 1017.67  4856.5 1017.75  4940.9 1016.29
  4954.9 1014.93  4978.2 1010.63  4984.6 1007.86  4993.6 1005.35  4993.8 1002.35
  4997.3 1002.35  4997.6 1005.35  5001.4 1007.96  5006.9 1010.28  5024.7 1015.50
  5039.4 1017.08  5053.4 1017.66  5076.6 1020.47  5099.9 1022.37  5177.0 1024.86
  5253.6 1022.34  5297.4 1021.76  5397.4 1022.37  5450.5 1024.50  5584.4 1031.95
#Mann=5,-1,0
  4602.9    0.05       0  4819.3    0.12       0  4993.6    0.07       0
  4997.6    0.12       0  5253.6    0.05       0
Bank Sta=4993.6,4997.6
Exp/Cntr=0.3,0.1

Type RM Length L Ch R = 1,22028,507,507,507
BEGIN DESCRIPTION:
UPSHAW CREEK 44.0
END DESCRIPTION:
XS GIS Cut Line= 3
      2871203.58     10182755.14      2871400.12     10182060.70
      2871393.59     10181606.76
#Sta/Elev= 30
  4507.0 1016.98  4561.3 1015.62  4623.4 1012.50  4680.3 1012.50  4685.8 1013.42
  4737.7 1013.20  4748.1 1013.95  4768.9 1012.91  4938.7 1011.15  4956.0 1008.92
  4972.7 1008.26  4977.9 1008.89  5009.8 1001.21  5010.1  998.21  5013.6  998.21
  5013.8 1001.21  5018.4 1006.53  5045.8 1010.81  5111.9 1010.41  5124.0 1009.41
  5132.7 1011.81  5208.7 1012.58  5277.2 1013.60  5386.3 1014.84  5426.3 1014.31
  5516.3 1015.70  5536.3 1016.79  5566.3 1016.41  5638.5 1018.52  5682.7 1020.73
#Mann=7,-1,0
  4507.0    0.05       0  4561.3    0.12       0  5009.8    0.07       0
  5013.8    0.12       0  5208.7    0.05       0  5277.2    0.12       0
  5638.5    0.05       0
Bank Sta=5009.8,5013.8
Exp/Cntr=0.3,0.1

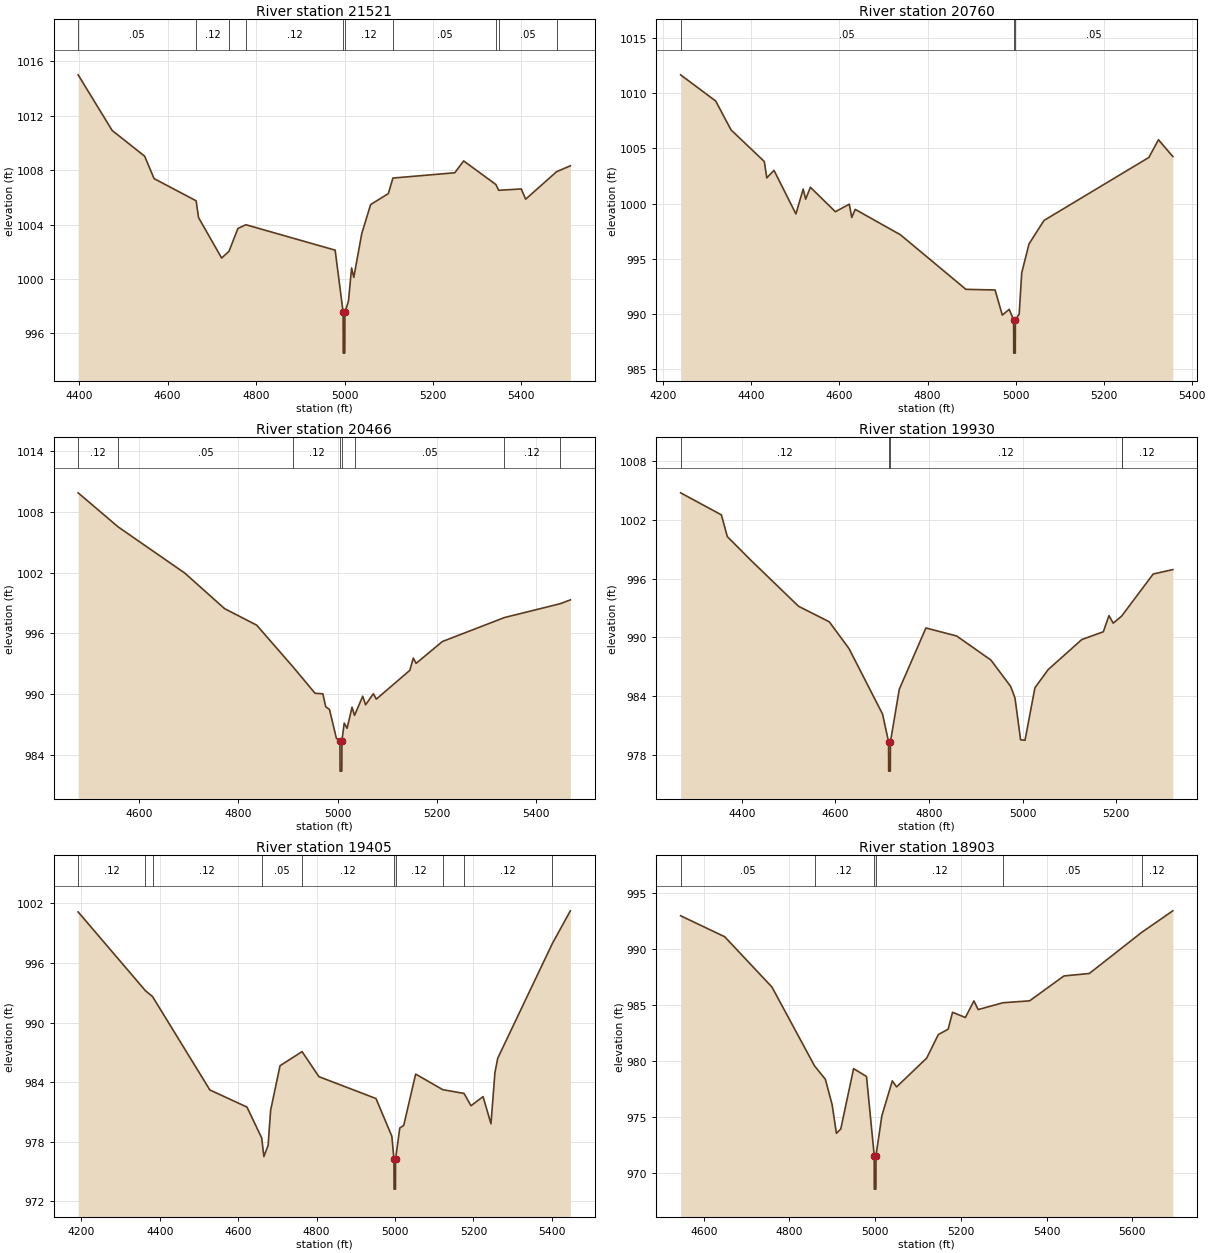
Type RM Length L Ch R = 1,21521,761,761,761
BEGIN DESCRIPTION:
UPSHAW CREEK 43.0
END DESCRIPTION:
XS GIS Cut Line= 3
      2871560.62     10182823.94      2871809.58     10182417.74
      2871770.27     10181782.27
#Sta/Elev= 30
  4397.6 1015.01  4474.5 1010.92  4548.0 1009.03  4569.3 1007.38  4664.4 1005.75
  4669.9 1004.51  4722.1 1001.54  4738.8 1002.04  4758.8 1003.71  4776.8 1003.99
  4978.8 1002.12  4996.9  997.55  4997.1  994.55  5000.6  994.55  5000.9  997.55
  5008.9  998.37  5016.0 1000.81  5021.0 1000.12  5039.0 1003.34  5059.0 1005.47
  5099.1 1006.28  5109.4 1007.42  5249.4 1007.81  5269.4 1008.68  5342.2 1006.95
  5348.7 1006.52  5399.7 1006.62  5409.7 1005.87  5479.7 1007.89  5510.7 1008.32
#Mann=10,-1,0
  4397.6    0.05       0  4664.4    0.12       0  4738.8    0.05       0
  4776.8    0.12       0  4996.9    0.07       0  5000.9    0.12       0
  5109.4    0.05       0  5342.2    0.12       0  5348.7    0.05       0
  5479.7    0.12       0
Bank Sta=4996.9,5000.9
Exp/Cntr=0.3,0.1

Type RM Length L Ch R = 1,20760,294,294,294
BEGIN DESCRIPTION:
UPSHAW CREEK 42.0
END DESCRIPTION:
XS GIS Cut Line= 3
      2872071.60     10183354.61      2872484.35     10182565.14
      2872594.94     10182366.73
#Sta/Elev= 30
  4239.2 1011.65  4318.9 1009.28  4353.7 1006.67  4429.3 1003.81  4434.9 1002.33
  4451.3 1003.01  4501.1  999.07  4517.6 1001.32  4523.2 1000.40  4534.0 1001.48
  4590.7  999.27  4622.3  999.95  4628.0  998.75  4635.8  999.48  4738.3  997.19
  4887.2  992.25  4953.5  992.19  4969.9  989.92  4985.6  990.44  4995.6  989.48
  4995.9  986.48  4999.4  986.48  4999.6  989.48  5008.2  990.01  5014.0  993.74
  5030.5  996.35  5064.6  998.48  5302.9 1004.18  5324.6 1005.78  5357.2 1004.26
#Mann=3,-1,0
  4239.2    0.05       0  4995.6    0.03       0  4999.6    0.05       0
Bank Sta=4995.6,4999.6
Exp/Cntr=0.3,0.1

Type RM Length L Ch R = 1,20466,536,536,536
BEGIN DESCRIPTION:
UPSHAW CREEK 41.0
END DESCRIPTION:
XS GIS Cut Line= 3
      2872291.07     10183380.81      2872655.68     10182753.11
      2872794.82     10182527.01
#Sta/Elev= 30
  4477.1 1009.91  4557.4 1006.55  4691.9 1001.97  4772.2  998.45  4836.7  996.82
  4909.8  992.70  4954.3  990.08  4970.0  990.03  4975.8  988.75  4983.3  988.48
  4997.3  985.63  5004.4  985.38  5004.7  982.38  5008.2  982.38  5008.4  985.38
  5013.0  987.13  5018.8  986.62  5028.8  988.71  5033.8  987.89  5050.3  989.79
  5056.1  988.94  5071.8  990.04  5077.6  989.50  5145.2  992.35  5152.1  993.56
  5157.9  993.04  5210.7  995.20  5335.6  997.57  5448.0  998.94  5468.5  999.32
#Mann=8,-1,0
  4477.1    0.12       0  4557.4    0.05       0  4909.8    0.12       0
  5004.4    0.07       0  5008.4    0.12       0  5033.8    0.05       0
  5335.6    0.12       0  5448.0    0.05       0
Bank Sta=5004.4,5008.4
Exp/Cntr=0.3,0.1

Type RM Length L Ch R = 1,19930,525,525,525
BEGIN DESCRIPTION:
UPSHAW CREEK 40.0
END DESCRIPTION:
XS GIS Cut Line= 3
      2873444.10     10183334.91      2873113.27     10182853.40
      2872864.67     10182457.60
#Sta/Elev= 30
  4269.5 1004.75  4356.6 1002.50  4369.3 1000.28  4420.1  997.84  4521.6  993.16
  4587.1  991.58  4629.2  988.85  4700.9  982.16  4713.8  979.33  4714.0  976.33
  4717.5  976.33  4717.8  979.33  4736.7  984.69  4793.6  990.95  4859.3  990.13
  4932.3  987.68  4974.7  984.98  4983.9  983.80  4995.9  979.53  5005.3  979.48
  5026.5  984.84  5054.8  986.70  5126.7  989.77  5172.6  990.56  5184.7  992.21
  5193.8  991.44  5211.5  992.15  5211.6  992.15  5279.2  996.46  5321.1  996.91
#Mann=5,-1,0
  4269.5    0.12       0  4713.8    0.07       0  4717.8    0.12       0
  5211.5    0.05       0  5211.6    0.12       0
Bank Sta=4713.8,4717.8
Exp/Cntr=0.3,0.1

Type RM Length L Ch R = 1,19405,502,502,502
BEGIN DESCRIPTION:
UPSHAW CREEK 39.0
END DESCRIPTION:
XS GIS Cut Line= 3
      2873676.69     10183131.85      2873421.18     10182506.18
      2873332.74     10181932.99
#Sta/Elev= 30
  4191.5 1001.13  4363.2  993.20  4381.3  992.61  4527.6  983.21  4622.2  981.49
  4659.8  978.38  4665.4  976.51  4676.2  977.64  4682.6  981.17  4706.6  985.65
  4762.8  987.07  4805.8  984.55  4951.4  982.35  4991.9  978.55  4997.3  976.23
  4997.6  973.23  5001.1  973.23  5001.3  976.23  5012.1  979.38  5022.2  979.64
  5052.6  984.81  5121.8  983.24  5176.1  982.86  5193.8  981.62  5224.6  982.54
  5244.8  979.81  5254.9  984.95  5262.0  986.40  5401.3  997.94  5447.3 1001.24
#Mann=10,-1,0
  4191.5    0.12       0  4363.2    0.05       0  4381.3    0.12       0
  4659.8    0.05       0  4762.8    0.12       0  4997.3    0.07       0
  5001.3    0.12       0  5121.8    0.05       0  5176.1    0.12       0
  5401.3    0.05       0
Bank Sta=4997.3,5001.3
Exp/Cntr=0.3,0.1

Type RM Length L Ch R = 1,18903,299,299,299
BEGIN DESCRIPTION:
UPSHAW CREEK 38.0
END DESCRIPTION:
XS GIS Cut Line= 3
      2873905.97     10182915.62      2873860.11     10182306.37
      2873876.49     10181769.19
#Sta/Elev= 30
  4546.1  992.95  4648.9  991.08  4759.2  986.59  4858.5  979.56  4883.8  978.36
  4899.6  976.10  4909.6  973.54  4919.7  973.92  4949.7  979.31  4979.8  978.61
  4997.8  971.56  4998.0  968.56  5001.7  968.56  5002.0  971.56  5015.6  975.10
  5040.0  978.22  5050.0  977.68  5120.2  980.25  5147.4  982.35  5170.3  982.83
  5180.6  984.34  5210.4  983.87  5230.4  985.35  5240.4  984.58  5298.3  985.19
  5360.4  985.36  5440.5  987.58  5499.7  987.80  5622.0  991.47  5694.5  993.39
#Mann=6,-1,0
  4546.1    0.05       0  4858.5    0.12       0  4997.8    0.07       0
  5002.0    0.12       0  5298.3    0.05       0  5622.0    0.12       0
Bank Sta=4997.8,5002
Exp/Cntr=0.3,0.1

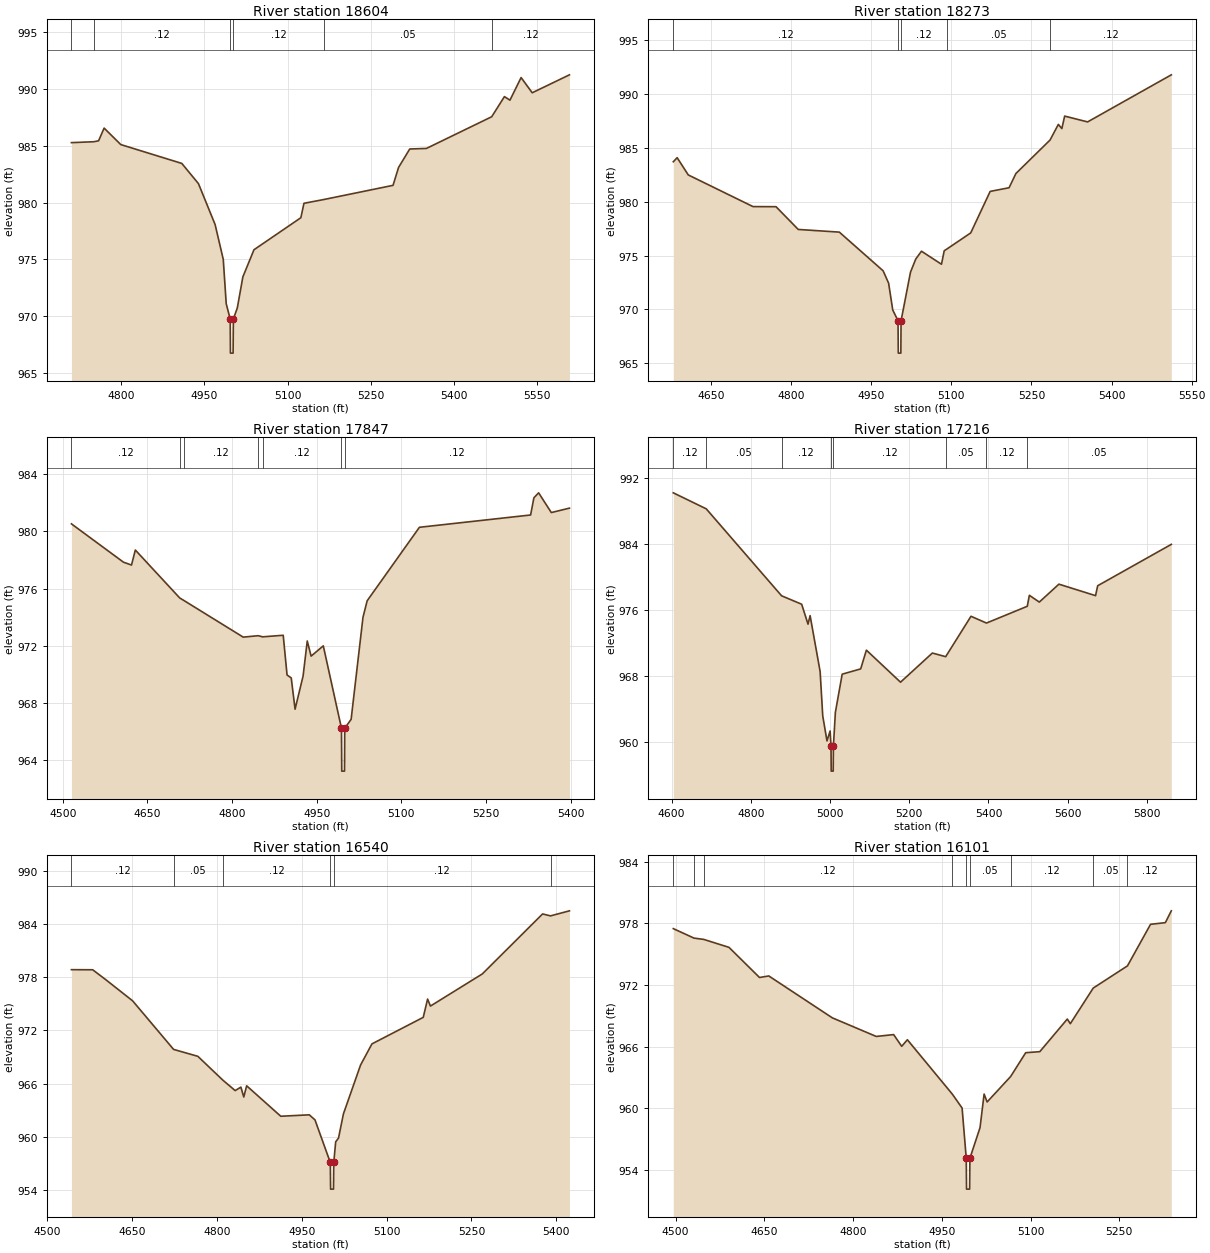
Type RM Length L Ch R = 1,18604,331,331,331
BEGIN DESCRIPTION:
UPSHAW CREEK 37.0
END DESCRIPTION:
XS GIS Cut Line= 3
      2874164.74     10182742.02      2874158.60     10182328.64
      2874119.03     10181846.29
#Sta/Elev= 30
  4710.3  985.28  4750.7  985.36  4759.2  985.44  4769.2  986.56  4799.2  985.11
  4909.2  983.45  4939.2  981.67  4969.2  978.07  4983.9  975.00  4989.2  971.10
  4996.4  969.75  4996.8  966.75  5001.6  966.75  5002.1  969.75  5009.2  970.73
  5019.2  973.46  5039.2  975.85  5123.7  978.67  5129.3  979.94  5165.9  980.28
  5289.8  981.52  5299.8  983.10  5319.9  984.72  5350.0  984.77  5467.6  987.56
  5490.5  989.33  5500.5  989.02  5520.6  991.01  5540.6  989.67  5607.7  991.25
#Mann=6,-1,0
  4710.3    0.05       0  4750.7    0.12       0  4996.4    0.07       0
  5002.1    0.12       0  5165.9    0.05       0  5467.6    0.12       0
Bank Sta=4996.4,5002.1
Exp/Cntr=0.3,0.1

Type RM Length L Ch R = 1,18273,426,426,426
BEGIN DESCRIPTION:
UPSHAW CREEK 36.0
END DESCRIPTION:
XS GIS Cut Line= 3
      2874305.70     10182653.09      2874473.58     10182447.62
      2874325.57     10181796.77
#Sta/Elev= 30
  4579.1  983.70  4586.3  984.08  4607.1  982.48  4728.4  979.54  4771.5  979.53
  4813.1  977.42  4890.1  977.17  4972.1  973.58  4982.4  972.43  4990.1  969.95
  5000.0  968.94  5000.5  965.94  5005.3  965.94  5005.7  968.94  5023.4  973.46
  5033.2  974.67  5043.9  975.40  5081.4  974.19  5086.5  975.44  5092.1  975.62
  5136.2  977.10  5172.6  980.95  5208.0  981.29  5220.8  982.61  5284.8  985.72
  5300.3  987.17  5306.9  986.78  5312.1  987.94  5355.1  987.40  5511.9  991.77
#Mann=5,-1,0
  4579.1    0.12       0  5000.0    0.07       0  5005.7    0.12       0
  5092.1    0.05       0  5284.8    0.12       0
Bank Sta=5000,5005.7
Exp/Cntr=0.3,0.1

Type RM Length L Ch R = 1,17847,631,631,631
BEGIN DESCRIPTION:
UPSHAW CREEK 35.0
END DESCRIPTION:
XS GIS Cut Line= 3
      2874455.68     10182653.12      2874895.21     10182250.68
      2875044.93     10182006.58
#Sta/Elev= 30
  4515.5  980.53  4607.7  977.85  4621.9  977.65  4628.7  978.70  4707.3  975.35
  4714.8  975.17  4819.8  972.61  4846.4  972.71  4854.2  972.63  4890.7  972.74
  4897.5  969.96  4904.9  969.76  4911.7  967.57  4925.9  969.89  4933.3  972.34
  4940.1  971.28  4961.7  972.00  4993.9  966.24  4994.4  963.24  4999.3  963.24
  4999.7  966.24  5011.0  966.86  5032.0  973.99  5039.4  975.15  5132.0  980.29
  5329.0  981.15  5334.8  982.35  5343.2  982.70  5365.7  981.32  5397.8  981.63
#Mann=7,-1,0
  4515.5    0.12       0  4707.3    0.05       0  4714.8    0.12       0
  4846.4    0.05       0  4854.2    0.12       0  4993.9    0.07       0
  4999.7    0.12       0
Bank Sta=4993.9,4999.7
Exp/Cntr=0.3,0.1

Type RM Length L Ch R = 1,17216,676,676,676
BEGIN DESCRIPTION:
Mapping XS 0a36fd7a
END DESCRIPTION:
XS GIS Cut Line= 2
      2874783.85     10183187.47      2875215.66     10182006.54
#Sta/Elev= 30
  4604.3  990.20  4687.5  988.26  4877.7  977.73  4928.4  976.71  4944.4  974.30
  4949.7  975.33  4975.0  968.56  4981.6  963.19  4992.3  960.16  5000.2  961.36
  5002.5  959.50  5003.0  956.50  5008.0  956.50  5008.5  959.50  5013.5  963.62
  5030.7  968.24  5077.4  968.88  5091.8  971.15  5178.0  967.27  5258.4  970.80
  5292.0  970.36  5355.9  975.25  5395.0  974.43  5498.0  976.46  5503.3  977.79
  5528.4  976.97  5577.9  979.14  5670.4  977.75  5675.8  978.95  5861.7  983.96
#Mann=8,-1,0
  4604.3    0.12       0  4687.5    0.05       0  4877.7    0.12       0
  5002.5    0.07       0  5008.5    0.12       0  5292.0    0.05       0
  5395.0    0.12       0  5498.0    0.05       0
Bank Sta=5002.5,5008.5
Exp/Cntr=0.3,0.1

Type RM Length L Ch R = 1,16540,439,439,439
BEGIN DESCRIPTION:
UPSHAW CREEK 34.0
END DESCRIPTION:
XS GIS Cut Line= 3
      2875373.45     10183020.46      2875452.06     10182381.71
      2875526.99     10182156.94
#Sta/Elev= 30
  4542.7  978.84  4580.3  978.83  4603.7  977.70  4650.9  975.33  4723.3  969.86
  4766.2  969.08  4810.5  966.39  4832.2  965.22  4842.3  965.61  4847.4  964.50
  4852.5  965.76  4912.8  962.33  4963.2  962.49  4973.3  961.92  5000.4  957.12
  5000.9  954.12  5006.0  954.12  5006.5  957.12  5009.9  959.45  5014.9  959.87
  5023.6  962.60  5053.9  968.10  5074.0  970.48  5164.7  973.47  5172.4  975.53
  5177.4  974.74  5269.1  978.36  5375.7  985.12  5389.7  984.90  5423.2  985.47
#Mann=6,-1,0
  4542.7    0.12       0  4723.3    0.05       0  4810.5    0.12       0
  5000.4    0.07       0  5006.5    0.12       0  5389.7    0.05       0
Bank Sta=5000.4,5006.5
Exp/Cntr=0.3,0.1

Type RM Length L Ch R = 1,16101,291,291,291
BEGIN DESCRIPTION:
UPSHAW CREEK 33.0
END DESCRIPTION:
XS GIS Cut Line= 3
      2875537.22     10183184.25      2875743.57     10182832.77
      2875805.68     10182403.12
#Sta/Elev= 30
  4496.3  977.48  4531.2  976.56  4547.9  976.43  4590.4  975.66  4642.0  972.73
  4657.7  972.88  4765.0  968.81  4839.3  967.00  4868.7  967.18  4882.3  966.04
  4891.9  966.68  4967.8  961.40  4984.4  960.04  4991.4  955.16  4991.9  952.16
  4997.1  952.16  4997.6  955.16  5014.7  958.14  5021.6  961.40  5026.7  960.63
  5066.5  963.11  5091.9  965.42  5115.7  965.52  5162.2  968.69  5167.3  968.24
  5206.0  971.70  5263.9  973.86  5302.9  977.90  5327.9  978.06  5338.0  979.21
#Mann=9,-1,0
  4496.3    0.12       0  4531.2    0.05       0  4547.9    0.12       0
  4967.8    0.05       0  4991.4    0.05       0  4997.6    0.05       0
  5066.5    0.12       0  5206.0    0.05       0  5263.9    0.12       0
Bank Sta=4991.4,4997.6
Exp/Cntr=0.3,0.1

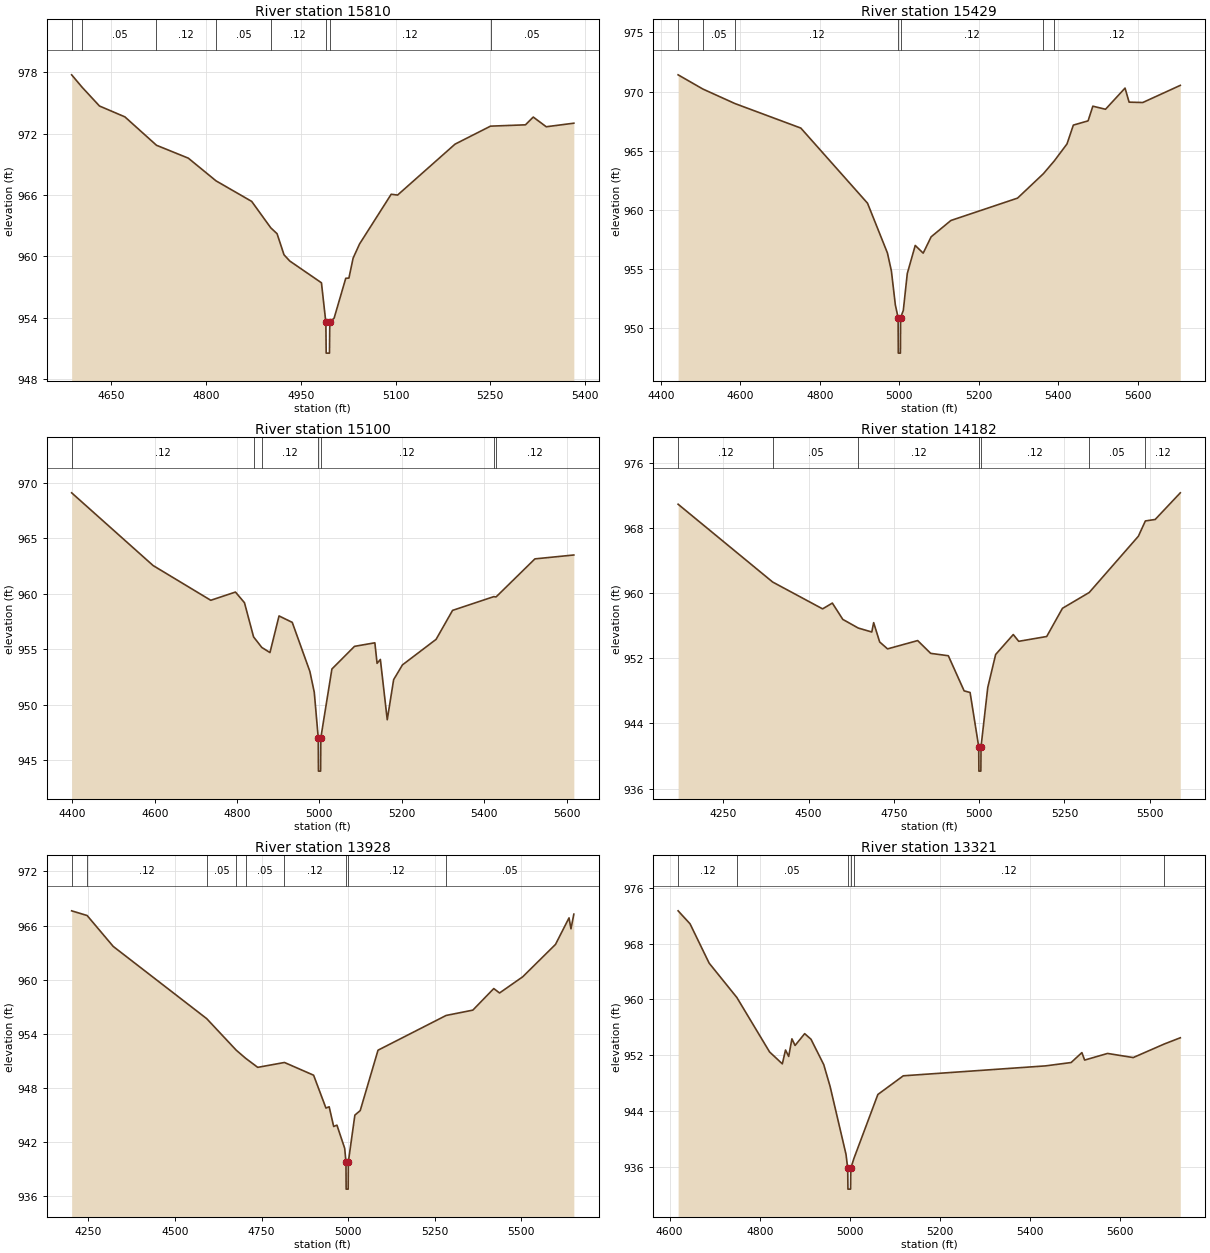
Type RM Length L Ch R = 1,15810,381,381,381
BEGIN DESCRIPTION:
UPSHAW CREEK 32.0
END DESCRIPTION:
XS GIS Cut Line= 3
      2875999.09     10183217.03      2876054.78     10182633.93
      2876002.36     10182430.84
#Sta/Elev= 30
  4587.0  977.74  4603.8  976.51  4631.1  974.69  4671.3  973.63  4721.4  970.85
  4771.8  969.59  4815.7  967.37  4872.2  965.36  4902.5  962.77  4912.4  962.20
  4923.4  960.14  4932.5  959.53  4982.7  957.40  4989.7  953.52  4990.2  950.52
  4995.4  950.52  4995.9  953.52  5002.8  953.95  5021.2  957.84  5026.2  957.86
  5032.9  959.82  5043.0  961.19  5093.2  966.06  5103.3  965.98  5194.3  970.96
  5250.5  972.72  5305.9  972.85  5318.2  973.61  5338.8  972.66  5382.5  973.01
#Mann=8,-1,0
  4587.0    0.12       0  4603.8    0.05       0  4721.4    0.12       0
  4815.7    0.05       0  4902.5    0.12       0  4989.7    0.07       0
  4995.9    0.12       0  5250.5    0.05       0
Bank Sta=4989.7,4995.9
Exp/Cntr=0.3,0.1

Type RM Length L Ch R = 1,15429,329,329,329
BEGIN DESCRIPTION:
UPSHAW CREEK 31.0
END DESCRIPTION:
XS GIS Cut Line= 3
      2876415.09     10183449.59      2876405.27     10182768.23
      2876120.46     10182260.82
#Sta/Elev= 30
  4443.3  971.41  4505.5  970.21  4586.4  968.98  4752.0  966.91  4919.8  960.56
  4969.8  956.36  4979.8  954.84  4989.8  951.96  4996.7  950.89  4997.2  947.89
  5002.5  947.89  5003.0  950.89  5009.8  951.50  5019.8  954.62  5039.8  956.99
  5059.8  956.34  5079.8  957.72  5129.5  959.10  5297.2  960.99  5362.1  963.05
  5389.7  964.14  5421.6  965.57  5437.5  967.16  5474.6  967.52  5486.6  968.76
  5518.5  968.50  5567.6  970.29  5577.8  969.10  5612.2  969.07  5706.6  970.52
#Mann=7,-1,0
  4443.3    0.12       0  4505.5    0.05       0  4586.4    0.12       0
  4996.7    0.07       0  5003.0    0.12       0  5362.1    0.05       0
  5389.7    0.12       0
Bank Sta=4996.7,5003
Exp/Cntr=0.3,0.1

Type RM Length L Ch R = 1,15100,918,918,918
BEGIN DESCRIPTION:
Mapping XS 848db8ef
END DESCRIPTION:
XS GIS Cut Line= 4
      2876759.03     10183370.94      2876755.76     10182954.94
      2876608.36     10182568.42      2876614.91     10182178.66
#Sta/Elev= 30
  4398.3  969.07  4596.1  962.52  4736.1  959.39  4796.1  960.13  4818.0  959.17
  4840.1  956.09  4860.1  955.14  4879.9  954.68  4901.9  957.98  4934.0  957.40
  4976.8  952.98  4987.5  951.10  4997.1  947.00  4997.6  944.00  5002.9  944.00
  5003.4  947.00  5030.3  953.20  5085.2  955.24  5134.6  955.56  5140.0  953.71
  5148.0  954.06  5164.7  948.63  5180.2  952.24  5201.6  953.57  5283.3  955.87
  5323.3  958.48  5423.5  959.72  5428.9  959.69  5523.3  963.12  5617.8  963.47
#Mann=7,-1,0
  4398.3    0.12       0  4840.1    0.05       0  4860.1    0.12       0
  4997.1    0.07       0  5003.4    0.12       0  5423.5    0.05       0
  5428.9    0.12       0
Bank Sta=4997.1,5003.4
Exp/Cntr=0.3,0.1

Type RM Length L Ch R = 1,14182,254,254,254
BEGIN DESCRIPTION:
UPSHAW CREEK 30.0
END DESCRIPTION:
XS GIS Cut Line= 3
      2876805.70     10183403.07      2877289.68     10182332.57
      2877394.49     10182054.17
#Sta/Elev= 30
  4117.3  970.89  4394.6  961.34  4540.9  958.05  4569.5  958.76  4600.1  956.76
  4645.3  955.70  4685.1  955.21  4690.6  956.36  4708.2  953.99  4731.3  953.14
  4819.6  954.16  4857.8  952.59  4909.5  952.30  4955.8  947.99  4973.3  947.79
  4998.6  941.14  4999.1  938.14  5004.9  938.14  5005.4  941.14  5025.1  948.40
  5048.2  952.45  5099.9  954.90  5115.9  954.07  5197.9  954.66  5244.1  958.12
  5322.6  960.06  5466.6  966.96  5487.2  968.84  5515.9  969.02  5589.6  972.29
#Mann=7,-1,0
  4117.3    0.12       0  4394.6    0.05       0  4645.3    0.12       0
  4998.6    0.07       0  5005.4    0.12       0  5322.6    0.05       0
  5487.2    0.12       0
Bank Sta=4998.6,5005.4
Exp/Cntr=0.3,0.1

Type RM Length L Ch R = 1,13928,607,607,607
BEGIN DESCRIPTION:
UPSHAW CREEK 29.0
END DESCRIPTION:
XS GIS Cut Line= 3
      2876988.32     10183397.17      2877191.42     10182840.30
      2877955.68     10182453.11
#Sta/Elev= 30
  4201.9  967.64  4246.6  967.12  4321.8  963.70  4591.6  955.70  4677.0  952.20
  4703.9  951.31  4739.0  950.30  4816.2  950.84  4900.3  949.43  4935.9  945.79
  4945.2  945.93  4958.2  943.75  4967.6  943.90  4990.0  941.33  4993.7  939.81
  4994.2  936.81  5000.0  936.81  5000.5  939.81  5019.4  945.01  5034.8  945.51
  5086.2  952.20  5282.8  956.05  5359.9  956.64  5420.3  959.03  5437.0  958.54
  5503.8  960.33  5598.5  963.92  5637.5  966.86  5643.1  965.65  5651.4  967.27
#Mann=9,-1,0
  4201.9    0.05       0  4246.6    0.12       0  4591.6    0.05       0
  4677.0    0.12       0  4703.9    0.05       0  4816.2    0.12       0
  4993.7    0.07       0  5000.5    0.12       0  5282.8    0.05       0
Bank Sta=4993.7,5000.5
Exp/Cntr=0.3,0.1

Type RM Length L Ch R = 1,13321,671,671,671
BEGIN DESCRIPTION:
UPSHAW CREEK 28.0
END DESCRIPTION:
XS GIS Cut Line= 3
      2877142.30     10183587.12      2877522.25     10183216.99
      2877849.80     10182732.22
#Sta/Elev= 30
  4618.8  972.68  4645.3  970.82  4687.7  965.20  4749.3  960.28  4822.0  952.49
  4850.3  950.79  4857.4  952.77  4864.4  951.85  4871.6  954.37  4878.6  953.42
  4899.9  955.11  4914.0  954.31  4942.3  950.68  4956.5  947.53  4991.7  937.86
  4995.5  935.87  4996.0  932.87  5001.9  932.87  5002.4  935.87  5009.2  937.24
  5062.5  946.41  5119.0  949.08  5434.9  950.50  5491.8  950.98  5515.7  952.40
  5521.8  951.33  5572.7  952.28  5629.7  951.69  5698.7  953.63  5734.3  954.52
#Mann=6,-1,0
  4618.8    0.12       0  4749.3    0.05       0  4995.5    0.05       0
  5002.4    0.05       0  5009.2    0.12       0  5698.7    0.05       0
Bank Sta=4995.5,5002.4
Exp/Cntr=0.3,0.1