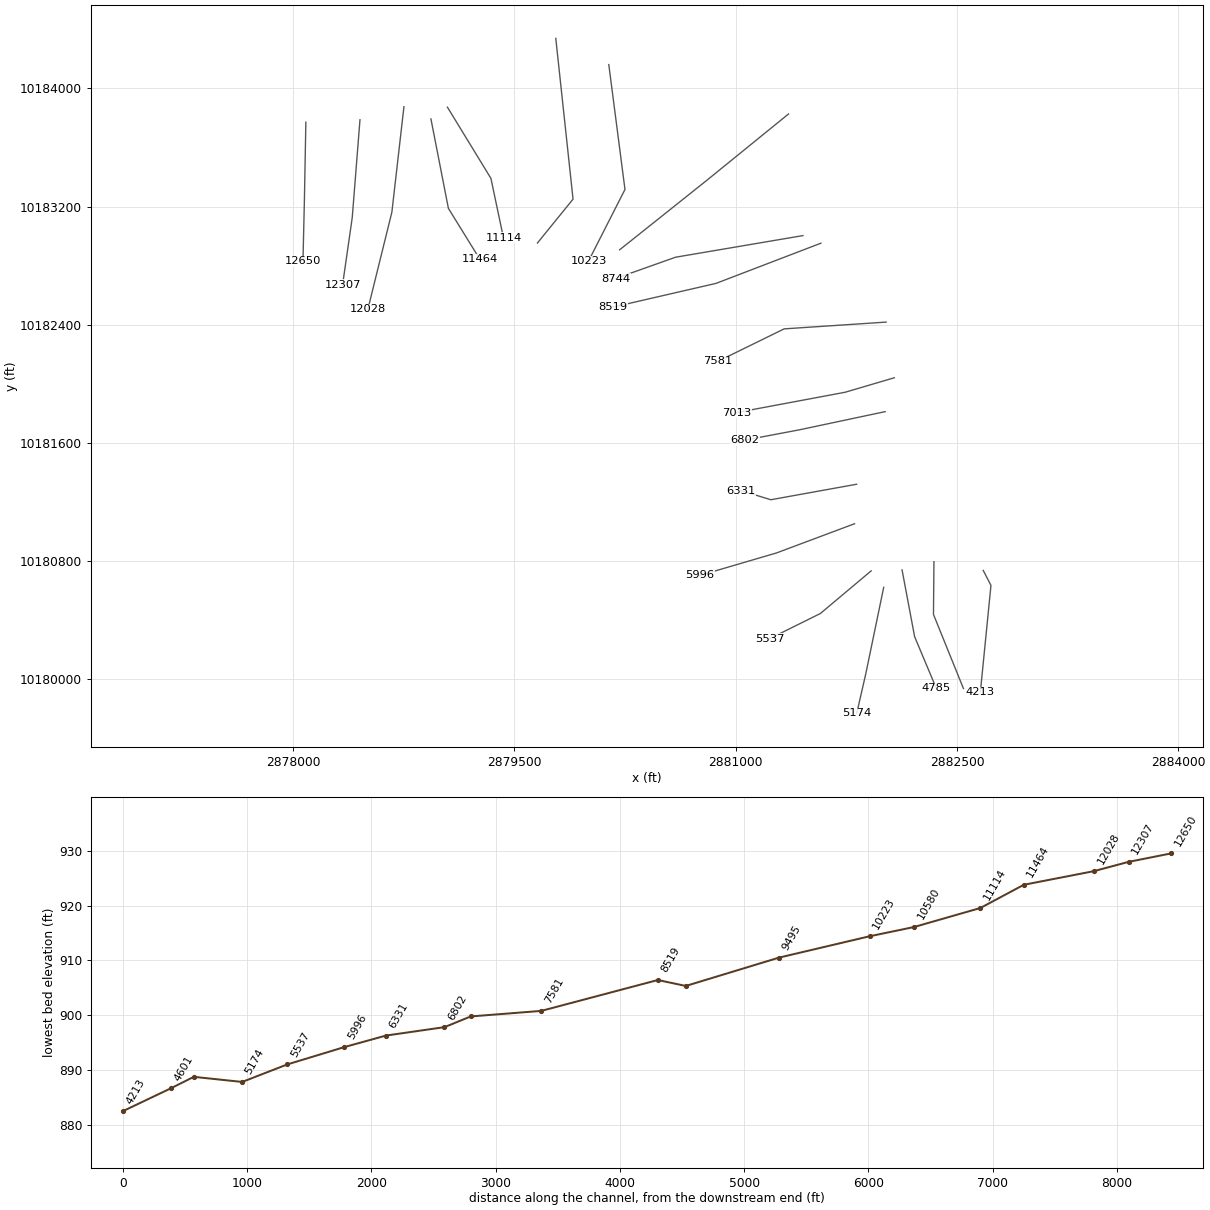
HEC-RAS study UPSHAW CREEK.prj: UPSHAW CREEK Base Level Engineering

--- UPSHAW CREEK.g01 (geometry) --- (continued)

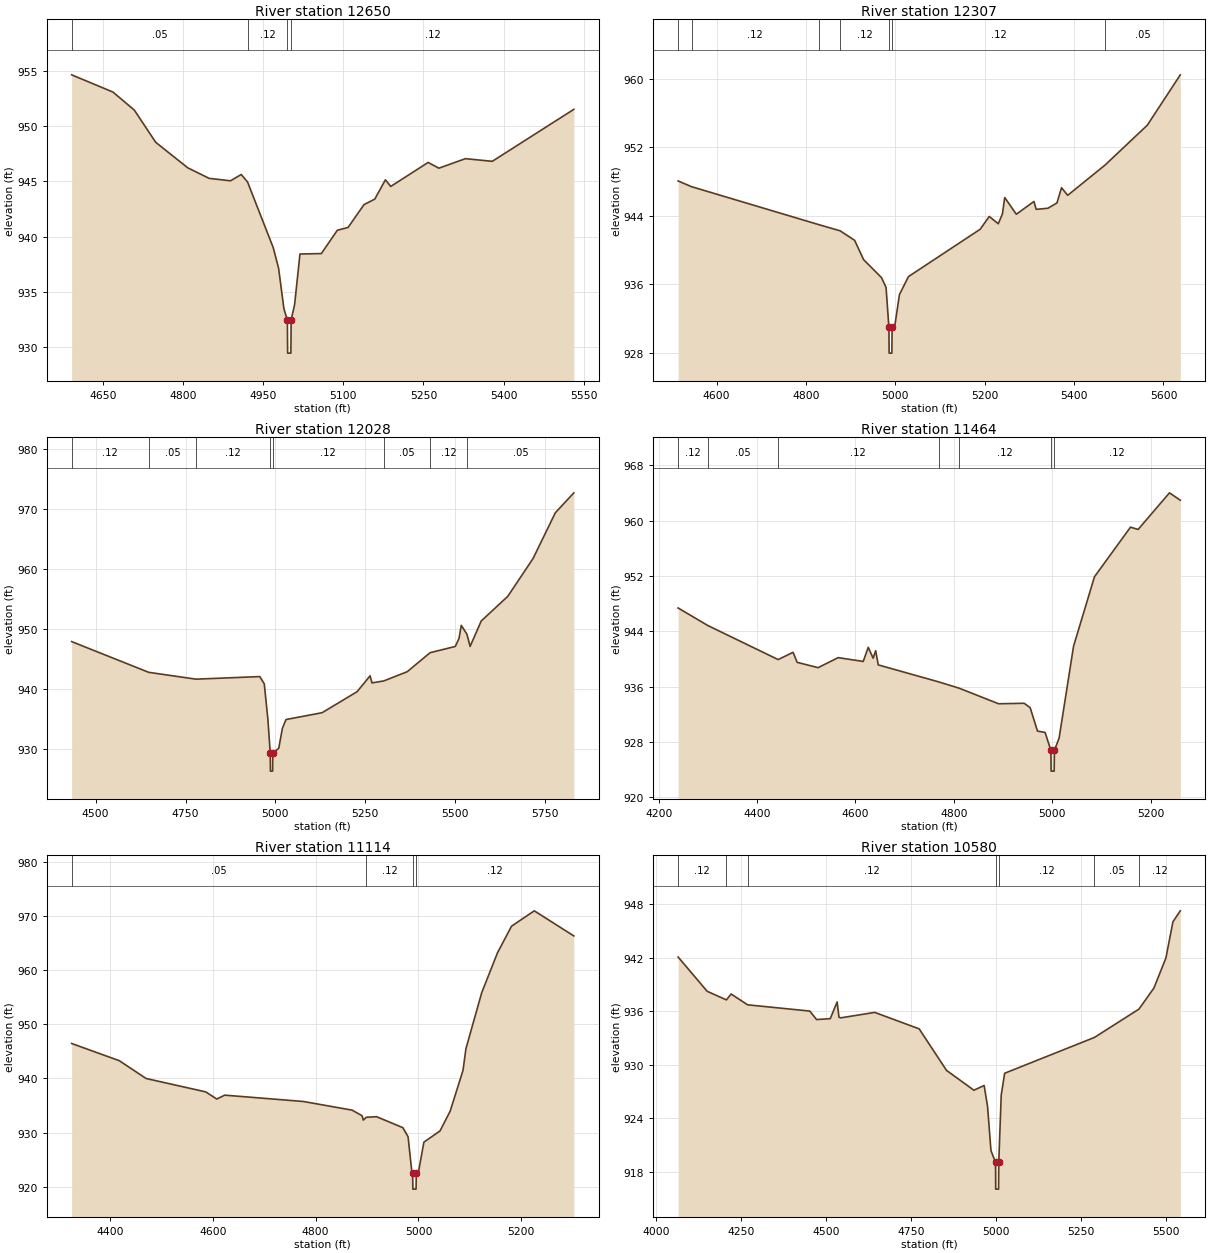
Type RM Length L Ch R = 1,12650,343,343,343
BEGIN DESCRIPTION:
UPSHAW CREEK 27.0
END DESCRIPTION:
XS GIS Cut Line= 3
      2878085.66     10183770.53      2878075.83     10183246.47
      2878066.00     10182830.44
#Sta/Elev= 30
  4591.4  954.64  4668.8  953.08  4708.8  951.45  4748.8  948.54  4808.9  946.23
  4848.9  945.28  4888.9  945.06  4908.9  945.63  4920.7  944.96  4968.9  939.01
  4978.9  937.15  4988.9  933.47  4995.3  932.48  4995.8  929.48  5001.9  929.48
  5002.4  932.48  5008.9  933.88  5018.9  938.44  5058.9  938.48  5088.9  940.59
  5108.9  940.84  5138.9  942.91  5158.9  943.40  5178.9  945.15  5188.9  944.55
  5258.9  946.72  5279.0  946.20  5328.7  947.06  5379.0  946.82  5531.7  951.52
#Mann=4,-1,0
  4591.4    0.05       0  4920.7    0.12       0  4995.3    0.07       0
  5002.4    0.12       0
Bank Sta=4995.3,5002.4
Exp/Cntr=0.3,0.1

Type RM Length L Ch R = 1,12307,279,279,279
BEGIN DESCRIPTION:
UPSHAW CREEK 26.0
END DESCRIPTION:
XS GIS Cut Line= 3
      2878452.53     10183786.91      2878400.12     10183125.27
      2878334.61     10182669.97
#Sta/Elev= 30
  4514.0  948.06  4544.0  947.39  4829.7  942.94  4876.7  942.23  4909.0  941.12
  4929.1  938.86  4969.2  936.76  4979.3  935.61  4985.7  930.94  4986.2  927.94
  4992.3  927.94  4992.8  930.94  4999.3  931.29  5009.3  934.79  5029.4  936.88
  5190.0  942.42  5210.2  943.91  5230.4  943.06  5239.7  944.21  5244.8  946.12
  5270.8  944.17  5310.2  945.66  5315.2  944.74  5341.5  944.87  5361.7  945.49
  5371.9  947.27  5385.7  946.38  5469.2  949.91  5563.8  954.57  5637.7  960.46
#Mann=7,-1,0
  4514.0    0.05       0  4544.0    0.12       0  4829.7    0.05       0
  4876.7    0.12       0  4985.7    0.07       0  4992.8    0.12       0
  5469.2    0.05       0
Bank Sta=4985.7,4992.8
Exp/Cntr=0.3,0.1

Type RM Length L Ch R = 1,12028,564,564,564
BEGIN DESCRIPTION:
UPSHAW CREEK 25.0
END DESCRIPTION:
XS GIS Cut Line= 3
      2878750.61     10183875.41      2878668.72     10183161.31
      2878505.68     10182503.08
#Sta/Elev= 30
  4433.3  947.87  4647.7  942.74  4779.1  941.60  4956.6  942.03  4969.1  940.82
  4979.2  934.88  4985.7  929.25  4986.2  926.25  4992.3  926.25  4992.8  929.25
  5009.4  930.07  5019.4  933.37  5029.5  934.86  5130.0  936.00  5227.3  939.51
  5263.5  942.16  5268.7  940.98  5301.4  941.30  5366.6  942.84  5430.5  946.02
  5500.5  947.06  5510.8  948.40  5517.1  950.58  5532.8  949.11  5541.7  947.07
  5572.6  951.31  5646.4  955.42  5716.8  961.74  5778.7  969.37  5830.2  972.70
#Mann=8,-1,0
  4433.3    0.12       0  4647.7    0.05       0  4779.1    0.12       0
  4985.7    0.07       0  4992.8    0.12       0  5301.4    0.05       0
  5430.5    0.12       0  5532.8    0.05       0
Bank Sta=4985.7,4992.8
Exp/Cntr=0.3,0.1

Type RM Length L Ch R = 1,11464,350,350,350
BEGIN DESCRIPTION:
UPSHAW CREEK 24.0
END DESCRIPTION:
XS GIS Cut Line= 3
      2878933.62     10183792.44      2879051.97     10183187.51
      2879264.88     10182843.57
#Sta/Elev= 30
  4239.4  947.36  4299.6  944.83  4442.7  939.90  4473.1  940.95  4481.4  939.50
  4524.0  938.73  4564.8  940.18  4615.7  939.63  4625.9  941.67  4635.9  940.10
  4641.0  941.18  4646.3  939.13  4768.8  936.68  4810.4  935.77  4890.9  933.51
  4942.9  933.58  4955.1  932.94  4970.0  929.56  4985.4  929.37  4997.2  926.77
  4997.7  923.77  5003.9  923.77  5004.4  926.77  5013.9  928.54  5043.3  941.83
  5085.8  951.87  5159.1  959.05  5174.5  958.71  5238.3  964.01  5260.3  962.94
#Mann=7,-1,0
  4239.4    0.12       0  4299.6    0.05       0  4442.7    0.12       0
  4768.8    0.05       0  4810.4    0.12       0  4997.2    0.07       0
  5004.4    0.12       0
Bank Sta=4997.2,5004.4
Exp/Cntr=0.3,0.1

Type RM Length L Ch R = 1,11114,534,534,534
BEGIN DESCRIPTION:
UPSHAW CREEK 23.0
END DESCRIPTION:
XS GIS Cut Line= 3
      2879045.43     10183872.09      2879340.22     10183390.60
      2879425.35     10182987.87
#Sta/Elev= 30
  4325.8  946.46  4418.4  943.28  4470.5  939.99  4586.6  937.51  4607.9  936.19
  4623.4  936.91  4776.2  935.74  4871.0  934.14  4890.4  933.10  4892.8  932.30
  4898.5  932.82  4918.5  932.93  4969.6  930.90  4979.8  929.22  4987.1  922.72
  4988.6  922.54  4989.1  919.54  4995.3  919.54  4995.8  922.54  5000.2  922.82
  5010.5  928.22  5041.9  930.30  5061.6  933.95  5086.6  941.50  5092.2  945.48
  5122.9  955.84  5153.5  963.20  5180.9  968.14  5225.1  970.98  5302.0  966.34
#Mann=4,-1,0
  4325.8    0.05       0  4898.5    0.12       0  4988.6    0.07       0
  4995.8    0.12       0
Bank Sta=4988.6,4995.8
Exp/Cntr=0.3,0.1

Type RM Length L Ch R = 1,10580,357,357,357
BEGIN DESCRIPTION:
UPSHAW CREEK 22.0
END DESCRIPTION:
XS GIS Cut Line= 3
      2879780.04     10184338.09      2879897.08     10183249.75
      2879655.66     10182953.08
#Sta/Elev= 30
  4064.9  942.06  4150.4  938.22  4207.1  937.26  4220.8  937.92  4269.3  936.71
  4452.1  936.01  4472.2  935.06  4512.4  935.16  4532.6  937.03  4538.1  935.32
  4543.1  935.25  4643.2  935.86  4773.9  934.02  4854.4  929.37  4934.9  927.15
  4965.0  927.68  4975.1  925.33  4985.1  920.39  4998.5  919.08  4999.0  916.08
  5007.5  916.08  5008.0  919.08  5015.3  926.62  5025.4  929.05  5289.5  933.06
  5420.4  936.23  5464.4  938.59  5499.6  941.94  5520.4  946.01  5542.0  947.23
#Mann=7,-1,0
  4064.9    0.12       0  4207.1    0.05       0  4269.3    0.12       0
  4998.5    0.07       0  5008.0    0.12       0  5289.5    0.05       0
  5420.4    0.12       0
Bank Sta=4998.5,5008
Exp/Cntr=0.3,0.1

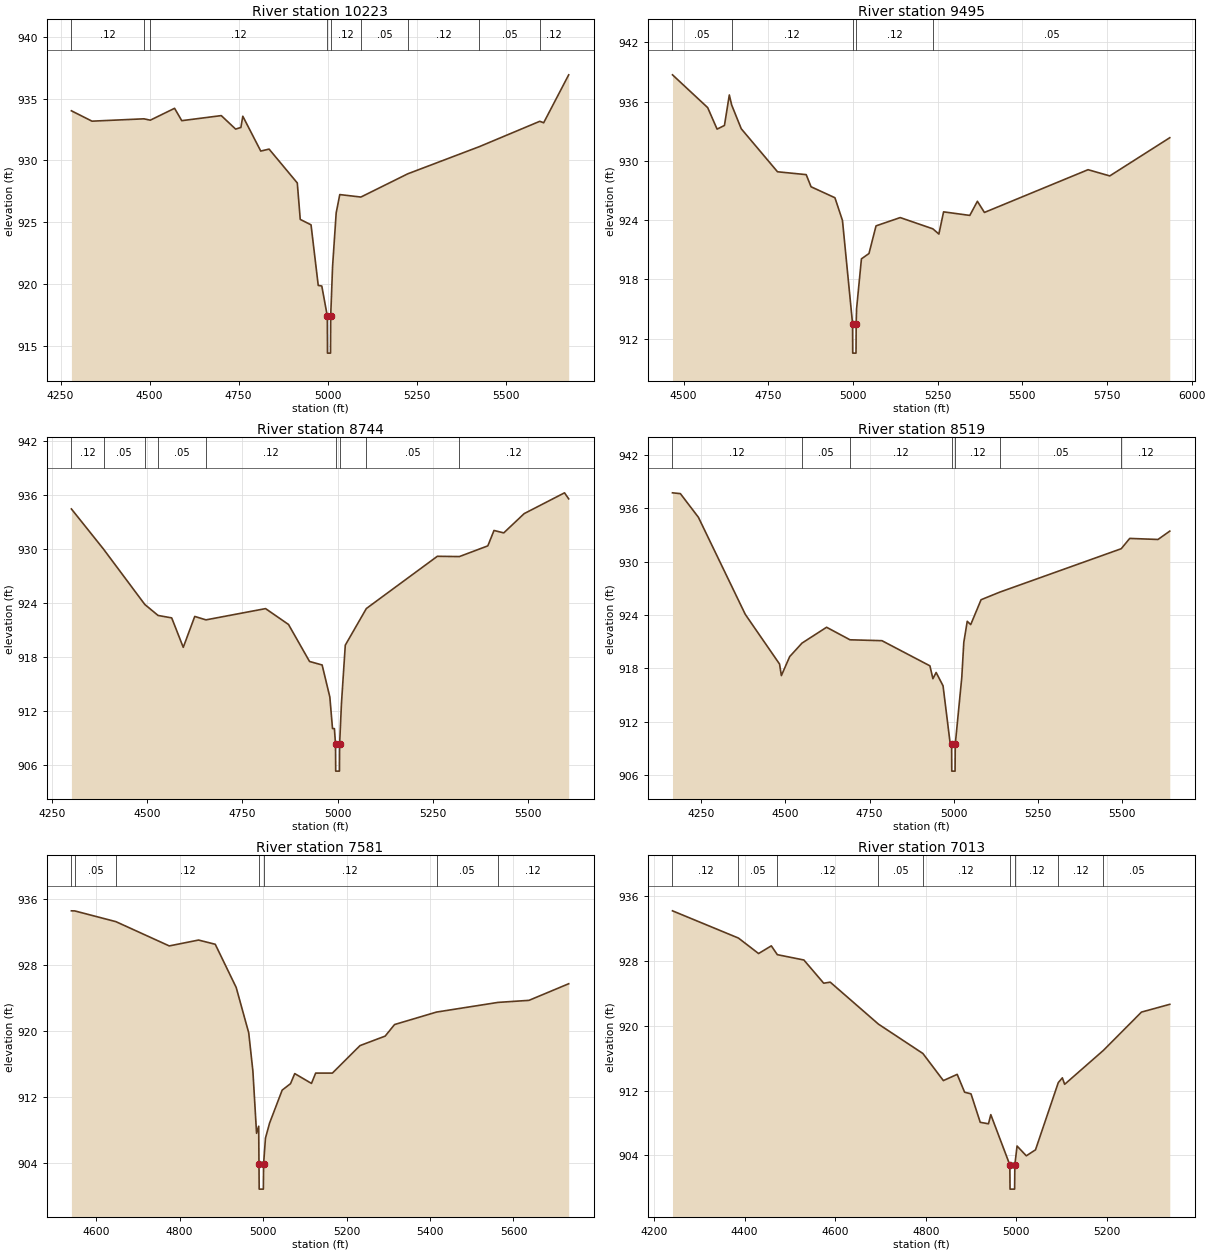
Type RM Length L Ch R = 1,10223,728,728,728
BEGIN DESCRIPTION:
UPSHAW CREEK 21.0
END DESCRIPTION:
XS GIS Cut Line= 3
      2880139.47     10184160.41      2880249.17     10183315.31
      2880001.92     10182830.51
#Sta/Elev= 30
  4280.6  934.01  4338.4  933.17  4484.3  933.36  4502.1  933.25  4570.3  934.21
  4590.5  933.21  4701.4  933.62  4741.7  932.53  4756.5  932.66  4761.9  933.57
  4812.3  930.75  4835.7  930.91  4914.9  928.17  4923.2  925.22  4953.5  924.78
  4973.7  919.88  4983.7  919.83  4999.2  917.40  4999.7  914.40  5008.2  914.40
  5008.7  917.40  5014.0  921.43  5024.1  925.75  5034.2  927.23  5093.5  927.03
  5225.1  928.91  5426.2  931.11  5595.9  933.16  5606.7  933.04  5677.0  936.92
#Mann=9,-1,0
  4280.6    0.12       0  4484.3    0.05       0  4502.1    0.12       0
  4999.2    0.07       0  5008.7    0.12       0  5093.5    0.05       0
  5225.1    0.12       0  5426.2    0.05       0  5595.9    0.12       0
Bank Sta=4999.2,5008.7
Exp/Cntr=0.3,0.1

Type RM Length L Ch R = 1,9495,751,751,751
BEGIN DESCRIPTION:
UPSHAW CREEK 20.0
END DESCRIPTION:
XS GIS Cut Line= 3
      2881358.00     10183826.25      2880804.42     10183377.50
      2880212.98     10182906.96
#Sta/Elev= 30
  4467.0  938.71  4570.9  935.39  4598.7  933.21  4620.4  933.58  4634.8  936.67
  4641.8  935.65  4670.0  933.25  4777.1  928.89  4861.8  928.60  4876.2  927.37
  4946.6  926.26  4968.9  923.96  4998.7  913.52  4999.2  910.52  5008.9  910.52
  5009.4  913.52  5010.6  915.02  5024.9  920.07  5047.2  920.61  5068.0  923.41
  5139.4  924.25  5235.9  923.11  5253.6  922.58  5267.5  924.83  5344.9  924.47
  5367.3  925.90  5388.1  924.77  5694.1  929.10  5758.2  928.47  5935.4  932.34
#Mann=5,-1,0
  4467.0    0.05       0  4641.8    0.12       0  4998.7    0.07       0
  5009.4    0.12       0  5235.9    0.05       0
Bank Sta=4998.7,5009.4
Exp/Cntr=0.3,0.1

Type RM Length L Ch R = 1,8744,225,225,225
BEGIN DESCRIPTION:
UPSHAW CREEK 19.0
END DESCRIPTION:
XS GIS Cut Line= 3
      2881455.67     10183003.11      2880591.51     10182856.67
      2880185.30     10182712.54
#Sta/Elev= 30
  4300.2  934.48  4384.6  930.02  4493.2  923.87  4528.1  922.65  4563.9  922.38
  4594.3  919.11  4624.5  922.54  4654.0  922.16  4810.7  923.41  4871.0  921.65
  4926.3  917.54  4959.4  917.15  4979.7  913.59  4986.7  910.09  4991.7  910.08
  4994.6  908.36  4995.1  905.36  5004.9  905.36  5005.4  908.36  5010.2  912.86
  5020.3  919.35  5075.7  923.42  5262.3  929.22  5320.3  929.19  5395.1  930.38
  5411.3  932.09  5436.9  931.82  5490.6  933.96  5596.7  936.27  5607.7  935.60
#Mann=9,-1,0
  4300.2    0.12       0  4384.6    0.05       0  4493.2    0.12       0
  4528.1    0.05       0  4654.0    0.12       0  4994.6    0.07       0
  5005.4    0.12       0  5075.7    0.05       0  5320.3    0.12       0
Bank Sta=4994.6,5005.4
Exp/Cntr=0.3,0.1

Type RM Length L Ch R = 1,8519,938,938,938
BEGIN DESCRIPTION:
UPSHAW CREEK 18.0
END DESCRIPTION:
XS GIS Cut Line= 3
      2881577.50     10182951.68      2880866.66     10182679.79
      2880169.82     10182519.49
#Sta/Elev= 30
  4164.9  937.76  4188.3  937.67  4241.8  935.01  4381.0  924.08  4482.7  918.49
  4488.1  917.19  4512.8  919.33  4549.4  920.85  4622.3  922.63  4691.8  921.22
  4786.6  921.12  4929.0  918.29  4937.9  916.84  4947.5  917.54  4968.0  916.04
  4988.5  909.75  4993.4  909.44  4993.9  906.44  5003.7  906.44  5004.2  909.44
  5023.6  916.99  5029.6  920.93  5039.8  923.30  5050.1  922.93  5080.9  925.73
  5136.1  926.58  5496.9  931.47  5522.1  932.63  5605.9  932.51  5641.0  933.45
#Mann=7,-1,0
  4164.9    0.12       0  4549.4    0.05       0  4691.8    0.12       0
  4993.4    0.07       0  5004.2    0.12       0  5136.1    0.05       0
  5496.9    0.12       0
Bank Sta=4993.4,5004.2
Exp/Cntr=0.3,0.1

Type RM Length L Ch R = 1,7581,568,568,568
BEGIN DESCRIPTION:
UPSHAW CREEK 17.0
END DESCRIPTION:
XS GIS Cut Line= 3
      2882019.68     10182417.74      2881328.52     10182371.88
      2880880.23     10182152.65
#Sta/Elev= 30
  4540.7  934.52  4548.7  934.51  4647.3  933.21  4775.2  930.27  4845.4  930.98
  4885.4  930.47  4935.6  925.24  4965.6  919.75  4975.6  915.13  4984.4  907.58
  4989.5  908.44  4990.2  903.82  4990.7  900.82  5000.7  900.82  5001.2  903.82
  5005.7  906.99  5015.7  908.83  5045.8  912.81  5065.8  913.59  5075.9  914.81
  5116.0  913.62  5126.0  914.87  5166.1  914.87  5232.3  918.20  5292.6  919.35
  5315.1  920.75  5415.6  922.26  5562.8  923.43  5637.3  923.68  5732.4  925.69
#Mann=7,-1,0
  4540.7    0.12       0  4548.7    0.05       0  4647.3    0.12       0
  4990.2    0.07       0  5001.2    0.12       0  5415.6    0.05       0
  5562.8    0.12       0
Bank Sta=4990.2,5001.2
Exp/Cntr=0.3,0.1

Type RM Length L Ch R = 1,7013,211,211,211
BEGIN DESCRIPTION:
UPSHAW CREEK 16.0
END DESCRIPTION:
XS GIS Cut Line= 3
      2882075.37     10182041.05      2881741.25     10181942.78
      2881004.25     10181805.20
#Sta/Elev= 30
  4240.9  934.22  4386.6  930.85  4431.0  928.94  4459.1  929.89  4472.4  928.80
  4531.0  928.14  4574.8  925.27  4589.2  925.40  4695.7  920.21  4793.8  916.58
  4839.0  913.23  4869.5  914.00  4885.9  911.79  4900.0  911.59  4920.4  908.07
  4938.6  907.89  4943.7  909.02  4985.7  902.81  4986.2  899.81  4996.3  899.81
  4996.8  902.81  5001.7  905.14  5022.1  903.93  5042.4  904.67  5092.7  912.98
  5101.7  913.57  5106.8  912.77  5192.4  916.97  5276.4  921.70  5338.9  922.66
#Mann=9,-1,0
  4240.9    0.12       0  4386.6    0.05       0  4472.4    0.12       0
  4695.7    0.05       0  4793.8    0.12       0  4985.7    0.05       0
  4996.8    0.12       0  5092.7    0.12       0  5192.4    0.05       0
Bank Sta=4985.7,4996.8
Exp/Cntr=0.3,0.1

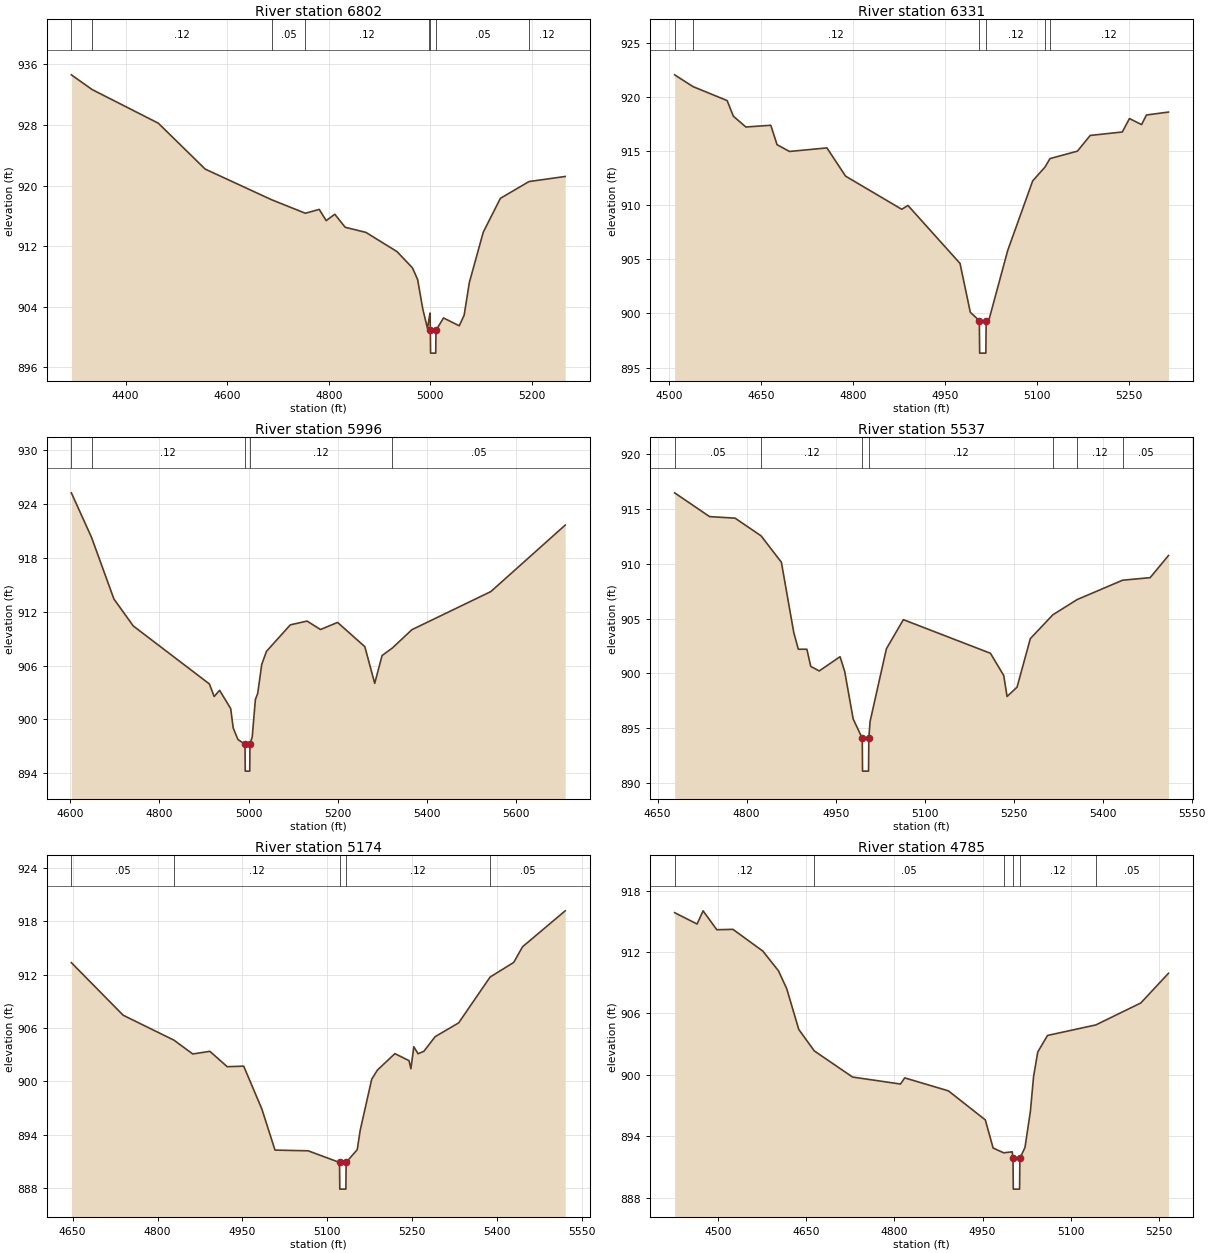
Type RM Length L Ch R = 1,6802,471,471,471
BEGIN DESCRIPTION:
UPSHAW CREEK 15.0
END DESCRIPTION:
XS GIS Cut Line= 3
      2882013.12     10181811.75      2881434.18     10181689.15
      2881060.27     10181618.56
#Sta/Elev= 30
  4293.2  934.63  4334.2  932.68  4464.4  928.24  4556.8  922.17  4687.7  918.12
  4753.9  916.34  4781.2  916.85  4795.0  915.37  4811.9  916.21  4832.3  914.49
  4873.2  913.81  4934.3  911.28  4964.9  909.12  4975.0  907.57  4985.2  903.67
  4994.3  901.14  4997.1  902.25  4999.4  903.16  5000.0  900.86  5000.5  897.86
  5010.6  897.86  5011.1  900.86  5025.9  902.51  5056.9  901.47  5066.6  902.88
  5076.8  907.19  5104.2  913.84  5137.9  918.31  5194.3  920.53  5265.5  921.20
#Mann=8,-1,0
  4293.2    0.05       0  4334.2    0.12       0  4687.7    0.05       0
  4753.9    0.12       0  4997.1    0.05       0  5000.0    0.05       0
  5011.1    0.05       0  5194.3    0.12       0
Bank Sta=5000,5011.1
Exp/Cntr=0.3,0.1

Type RM Length L Ch R = 1,6331,335,335,335
BEGIN DESCRIPTION:
UPSHAW CREEK 14.0
END DESCRIPTION:
XS GIS Cut Line= 3
      2881819.90     10181320.42      2881238.32     10181215.51
      2881033.76     10181277.81
#Sta/Elev= 30
  4509.0  922.04  4539.0  920.95  4594.6  919.66  4604.7  918.22  4625.1  917.22
  4665.7  917.38  4675.9  915.59  4696.2  914.96  4757.2  915.29  4787.6  912.68
  4879.1  909.62  4889.3  909.97  4974.1  904.62  4990.9  900.10  5005.6  899.33
  5006.1  896.33  5016.2  896.33  5016.7  899.33  5021.4  899.44  5051.8  905.81
  5092.5  912.24  5112.6  913.52  5120.7  914.30  5165.4  914.99  5186.3  916.44
  5238.6  916.76  5250.2  918.00  5270.0  917.44  5277.9  918.33  5313.8  918.60
#Mann=6,-1,0
  4509.0    0.05       0  4539.0    0.12       0  5005.6    0.07       0
  5016.7    0.12       0  5112.6    0.05       0  5120.7    0.12       0
Bank Sta=5005.6,5016.7
Exp/Cntr=0.3,0.1

Type RM Length L Ch R = 1,5996,459,459,459
BEGIN DESCRIPTION:
UPSHAW CREEK 13.0
END DESCRIPTION:
XS GIS Cut Line= 3
      2881805.72     10181053.12      2881276.11     10180855.27
      2880755.66     10180703.10
#Sta/Elev= 30
  4602.5  925.26  4647.8  920.29  4697.9  913.43  4741.3  910.42  4912.1  903.95
  4922.8  902.55  4935.0  903.24  4959.9  901.20  4965.5  899.04  4976.2  897.75
  4992.0  897.23  4992.5  894.23  5002.6  894.23  5003.1  897.23  5008.2  898.06
  5015.2  902.20  5020.5  902.91  5029.5  906.13  5040.2  907.59  5093.6  910.54
  5131.1  910.96  5161.4  910.02  5199.6  910.81  5260.7  908.11  5282.9  904.02
  5299.4  907.12  5322.3  907.95  5366.3  910.00  5543.4  914.25  5710.1  921.66
#Mann=5,-1,0
  4602.5    0.05       0  4647.8    0.12       0  4992.0    0.07       0
  5003.1    0.12       0  5322.3    0.05       0
Bank Sta=4992,5003.1
Exp/Cntr=0.3,0.1

Type RM Length L Ch R = 1,5537,363,363,363
BEGIN DESCRIPTION:
UPSHAW CREEK 12.0
END DESCRIPTION:
XS GIS Cut Line= 3
      2881918.13     10180734.07      2881574.19     10180445.82
      2881230.49     10180275.60
#Sta/Elev= 30
  4678.6  916.47  4737.5  914.30  4780.5  914.16  4824.2  912.55  4858.5  910.14
  4879.4  903.72  4887.1  902.20  4901.5  902.20  4908.0  900.64  4922.3  900.22
  4957.4  901.52  4965.2  900.18  4979.5  895.84  4994.8  894.08  4995.3  891.08
  5005.4  891.08  5005.9  894.08  5008.0  895.61  5035.5  902.24  5064.1  904.90
  5210.9  901.83  5233.3  899.80  5238.9  897.89  5255.7  898.74  5278.1  903.17
  5316.0  905.34  5356.9  906.73  5433.7  908.50  5480.0  908.73  5510.9  910.75
#Mann=7,-1,0
  4678.6    0.05       0  4824.2    0.12       0  4994.8    0.07       0
  5005.9    0.12       0  5316.0    0.05       0  5356.9    0.12       0
  5433.7    0.05       0
Bank Sta=4994.8,5005.9
Exp/Cntr=0.3,0.1

Type RM Length L Ch R = 1,5174,389,389,389
BEGIN DESCRIPTION:
UPSHAW CREEK 11.0
END DESCRIPTION:
XS GIS Cut Line= 3
      2882003.31     10180622.75      2881882.05     10180038.57
      2881820.31     10179769.70
#Sta/Elev= 30
  4647.8  913.36  4739.3  907.45  4829.2  904.64  4862.3  903.09  4892.5  903.39
  4923.2  901.66  4952.3  901.72  4984.5  896.88  5007.6  892.28  5066.2  892.20
  5121.6  890.89  5122.1  887.89  5132.8  887.89  5133.3  890.89  5152.9  892.33
  5158.1  894.50  5178.5  900.26  5188.7  901.29  5219.4  903.13  5244.4  902.34
  5247.7  901.43  5252.9  903.90  5260.3  903.12  5270.6  903.39  5290.6  905.04
  5332.1  906.59  5387.6  911.74  5429.4  913.39  5445.0  915.15  5520.3  919.19
#Mann=5,-1,0
  4647.8    0.05       0  4829.2    0.12       0  5121.6    0.07       0
  5133.3    0.12       0  5387.6    0.05       0
Bank Sta=5121.6,5133.3
Exp/Cntr=0.3,0.1

Type RM Length L Ch R = 1,4785,184,184,184
BEGIN DESCRIPTION:
UPSHAW CREEK 10.0
END DESCRIPTION:
XS GIS Cut Line= 3
      2882127.77     10180740.64      2882212.94     10180288.59
      2882360.33     10179938.13
#Sta/Elev= 30
  4426.1  915.86  4464.3  914.75  4474.5  916.04  4497.9  914.19  4525.3  914.23
  4576.2  912.10  4602.8  910.17  4616.9  908.41  4637.3  904.44  4663.7  902.34
  4728.9  899.78  4810.3  899.10  4817.6  899.70  4892.0  898.43  4954.7  895.59
  4968.0  892.84  4986.0  892.37  5000.5  892.47  5001.8  891.82  5002.3  888.82
  5013.0  888.82  5013.5  891.82  5022.2  892.90  5031.4  896.43  5036.8  899.83
  5043.9  902.23  5060.5  903.85  5142.7  904.88  5219.3  907.03  5266.3  909.93
#Mann=6,-1,0
  4426.1    0.12       0  4663.7    0.05       0  4986.0    0.12       0
  5001.8    0.07       0  5013.5    0.12       0  5142.7    0.05       0
Bank Sta=5001.8,5013.5
Exp/Cntr=0.3,0.1

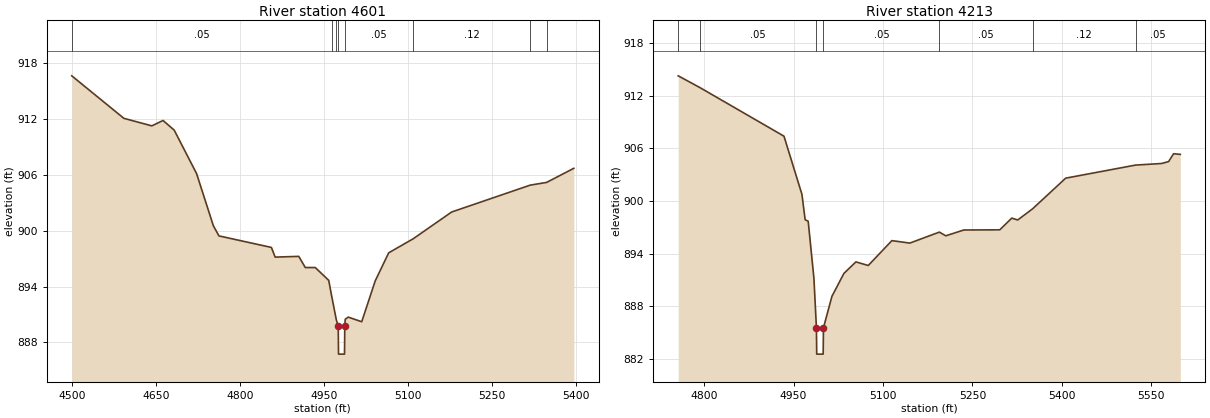
Type RM Length L Ch R = 1,4601,388,388,388
BEGIN DESCRIPTION:
Mapping XS ae8b79e9
END DESCRIPTION:
XS GIS Cut Line= 3
      2882343.96     10180796.28      2882340.69     10180439.27
      2882543.78     10179938.08
#Sta/Elev= 30
  4499.1  916.66  4592.3  912.09  4642.3  911.28  4662.3  911.86  4682.3  910.82
  4722.3  906.15  4752.3  900.54  4762.3  899.45  4856.1  898.21  4862.8  897.17
  4905.0  897.25  4916.7  896.05  4934.5  896.05  4958.6  894.67  4963.6  893.06
  4972.2  890.42  4975.6  889.74  4976.1  886.74  4986.8  886.74  4987.3  889.74
  4988.1  890.49  4993.5  890.72  5017.6  890.22  5041.7  894.61  5065.8  897.63
  5109.6  899.14  5178.4  902.02  5319.0  904.91  5348.2  905.20  5396.9  906.72
#Mann=8,-1,0
  4499.1    0.05       0  4963.6    0.12       0  4972.2    0.05       0
  4975.6    0.05       0  4987.3    0.05       0  5109.6    0.12       0
  5319.0    0.05       0  5348.2    0.12       0
Bank Sta=4975.6,4987.3
Exp/Cntr=0.3,0.1

Type RM Length L Ch R = 1,4213,525,525,525
BEGIN DESCRIPTION:
UPSHAW CREEK 9.0
END DESCRIPTION:
XS GIS Cut Line= 3
      2882678.07     10180737.36      2882730.49     10180635.80
      2882658.42     10179911.87
#Sta/Elev= 30
  4756.7  914.24  4793.1  912.90  4934.0  907.37  4964.1  900.75  4969.5  897.86
  4974.6  897.69  4984.2  891.20  4988.4  885.56  4988.9  882.56  4999.7  882.56
  5000.2  885.56  5014.4  889.14  5034.5  891.75  5054.6  893.06  5075.3  892.65
  5114.9  895.48  5145.0  895.20  5194.5  896.45  5205.3  896.03  5235.5  896.69
  5295.8  896.71  5315.9  898.04  5325.9  897.83  5350.8  899.10  5406.3  902.59
  5523.5  904.08  5567.1  904.26  5578.9  904.48  5587.2  905.37  5598.5  905.30
#Mann=7,-1,0
  4756.7    0.12       0  4793.1    0.05       0  4988.4    0.07       0
  5000.2    0.05       0  5194.5    0.05       0  5350.8    0.12       0
  5523.5    0.05       0
Bank Sta=4988.4,5000.2
Exp/Cntr=0.3,0.1