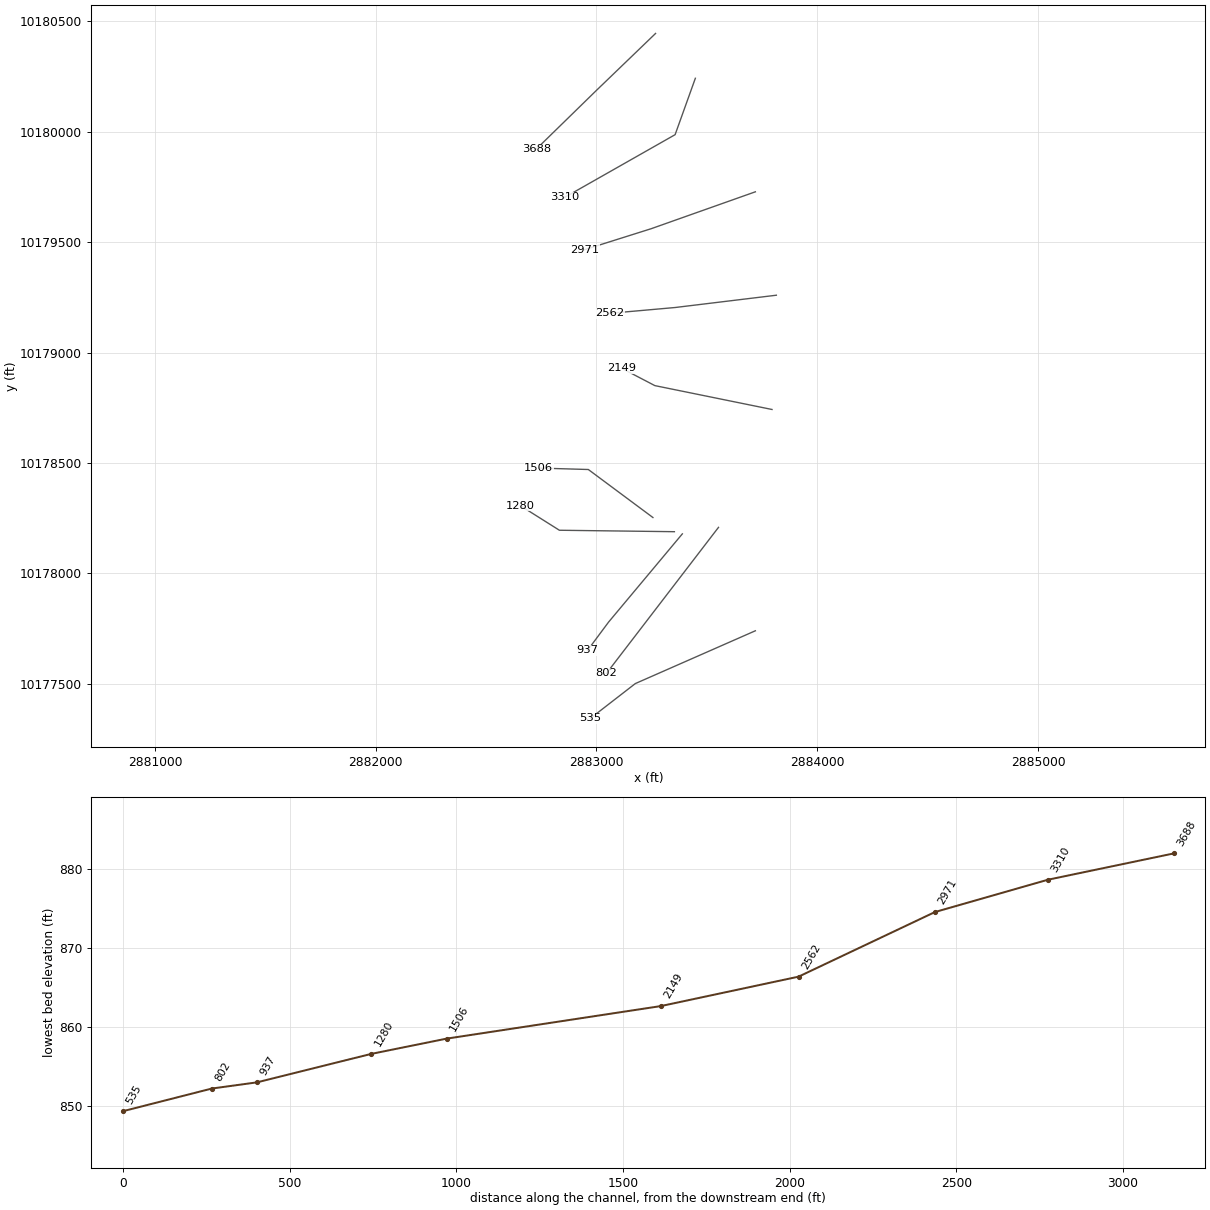
HEC-RAS study UPSHAW CREEK.prj: UPSHAW CREEK Base Level Engineering

--- UPSHAW CREEK.g01 (geometry) --- (continued)

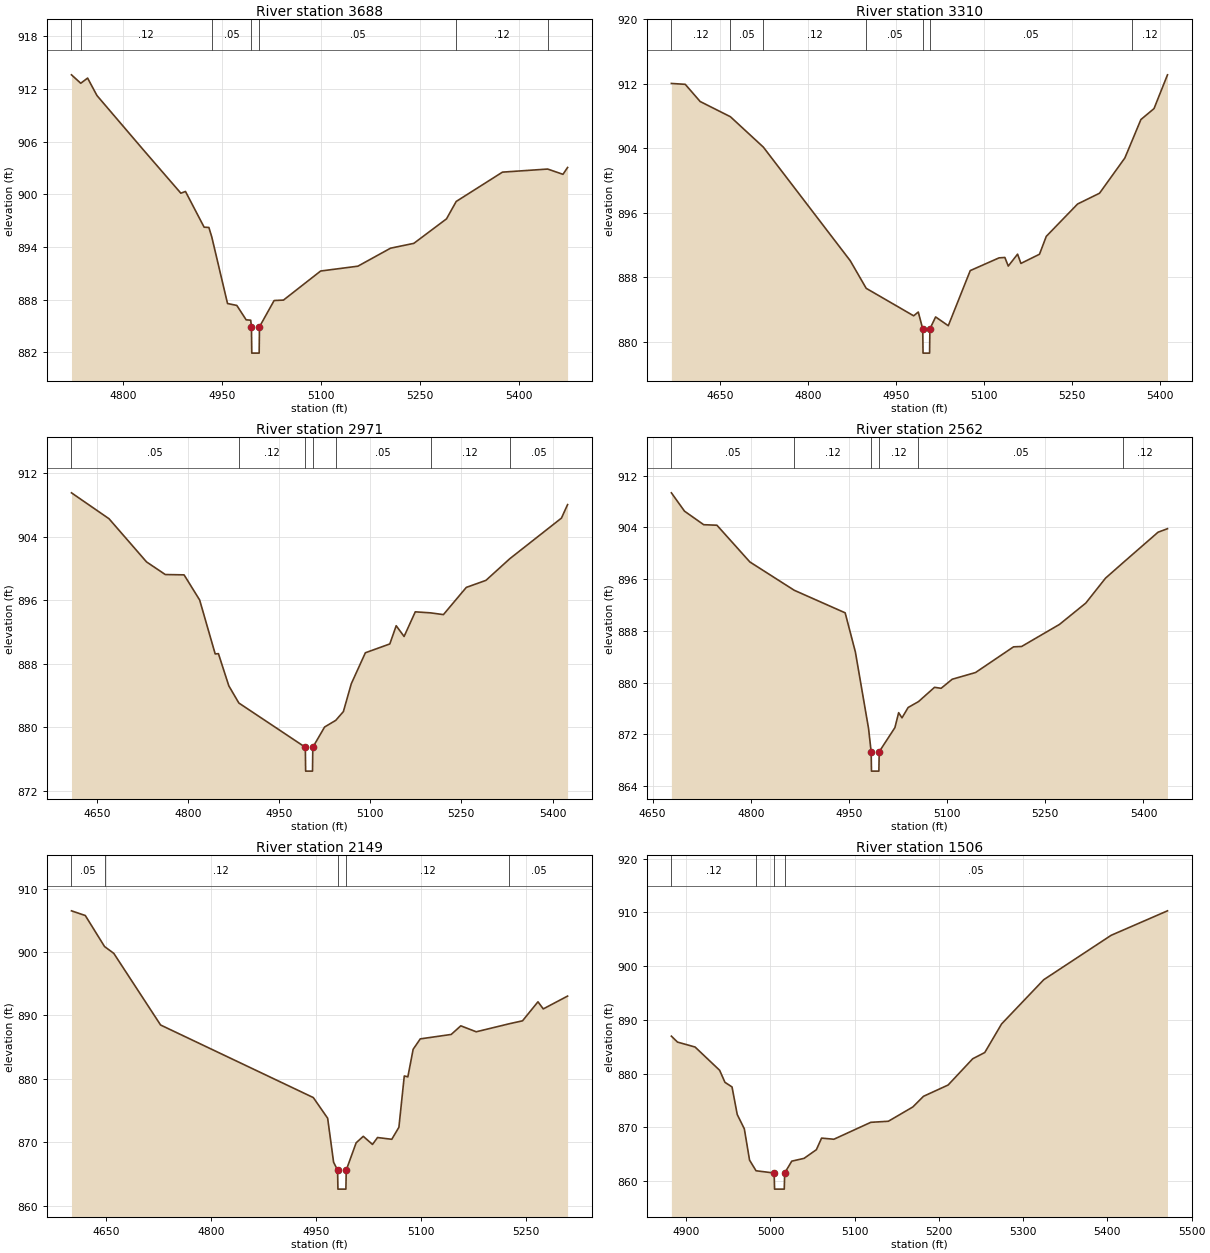
Type RM Length L Ch R = 1,3688,378,378,378
BEGIN DESCRIPTION:
UPSHAW CREEK 8.0
END DESCRIPTION:
XS GIS Cut Line= 3
      2883267.67     10180445.80      2883002.36     10180190.32
      2882727.24     10179921.75
#Sta/Elev= 30
  4721.6  913.60  4735.7  912.64  4746.1  913.23  4760.3  911.24  4831.0  905.03
  4887.6  900.12  4894.6  900.32  4922.9  896.25  4930.1  896.22  4934.5  895.14
  4958.4  887.56  4972.5  887.34  4986.7  885.70  4993.6  885.66  4994.7  884.91
  4995.2  881.91  5006.4  881.91  5006.9  884.91  5029.1  887.90  5043.3  887.95
  5099.7  891.26  5156.2  891.81  5205.8  893.86  5241.1  894.41  5290.7  897.20
  5305.4  899.18  5375.6  902.52  5444.2  902.87  5467.4  902.27  5474.4  903.05
#Mann=7,-1,0
  4721.6    0.05       0  4735.7    0.12       0  4934.5    0.05       0
  4994.7    0.05       0  5006.9    0.05       0  5305.4    0.12       0
  5444.2    0.05       0
Bank Sta=4994.7,5006.9
Exp/Cntr=0.3,0.1

Type RM Length L Ch R = 1,3310,339,339,339
BEGIN DESCRIPTION:
UPSHAW CREEK 7.0
END DESCRIPTION:
XS GIS Cut Line= 3
      2883447.84     10180242.72      2883356.13     10179987.23
      2882855.71     10179703.12
#Sta/Elev= 30
  4566.6  912.04  4590.3  911.93  4615.7  909.80  4667.4  907.91  4723.6  904.14
  4872.0  890.04  4899.2  886.62  4980.2  883.21  4988.1  883.68  4995.7  881.58
  4996.2  878.58  5007.4  878.58  5007.9  881.58  5017.7  883.07  5039.3  881.98
  5076.8  888.82  5126.0  890.40  5135.9  890.45  5141.7  889.38  5157.6  890.86
  5163.3  889.71  5195.0  890.85  5206.6  893.07  5260.0  897.08  5297.5  898.42
  5340.7  902.79  5352.7  904.87  5368.1  907.56  5390.5  908.92  5413.5  913.11
#Mann=7,-1,0
  4566.6    0.12       0  4667.4    0.05       0  4723.6    0.12       0
  4899.2    0.05       0  4995.7    0.05       0  5007.9    0.05       0
  5352.7    0.12       0
Bank Sta=4995.7,5007.9
Exp/Cntr=0.3,0.1

Type RM Length L Ch R = 1,2971,409,409,409
BEGIN DESCRIPTION:
UPSHAW CREEK 6.0
END DESCRIPTION:
XS GIS Cut Line= 3
      2883719.69     10179728.45      2883248.03     10179561.40
      2882946.71     10179466.42
#Sta/Elev= 30
  4608.5  909.50  4670.3  906.24  4732.0  900.81  4762.9  899.22  4793.8  899.18
  4819.4  896.02  4845.0  889.23  4850.3  889.27  4867.4  885.22  4883.9  883.06
  4993.3  877.49  4993.8  874.49  5005.1  874.49  5005.6  877.49  5025.0  880.04
  5043.4  880.88  5055.9  881.98  5068.9  885.48  5092.1  889.38  5132.3  890.49
  5142.8  892.78  5155.8  891.43  5174.2  894.53  5199.3  894.40  5220.5  894.18
  5258.1  897.60  5290.5  898.49  5329.7  901.21  5414.7  906.32  5424.8  908.02
#Mann=7,-1,0
  4608.5    0.05       0  4883.9    0.12       0  4993.3    0.07       0
  5005.6    0.12       0  5043.4    0.05       0  5199.3    0.12       0
  5329.7    0.05       0
Bank Sta=4993.3,5005.6
Exp/Cntr=0.3,0.1

Type RM Length L Ch R = 1,2562,413,413,413
BEGIN DESCRIPTION:
UPSHAW CREEK 5.0
END DESCRIPTION:
XS GIS Cut Line= 3
      2883814.74     10179260.05      2883356.13     10179204.36
      2883061.37     10179178.16
#Sta/Elev= 30
  4678.8  909.36  4698.9  906.52  4728.2  904.43  4748.4  904.35  4798.7  898.67
  4866.5  894.29  4944.3  890.80  4959.9  884.75  4980.0  872.93  4984.0  869.32
  4984.5  866.32  4995.8  866.32  4996.3  869.32  5020.3  873.05  5026.0  875.36
  5031.1  874.56  5040.5  876.16  5056.3  877.07  5080.8  879.28  5090.9  879.13
  5107.8  880.53  5143.5  881.57  5201.5  885.54  5213.9  885.60  5271.7  889.01
  5311.9  892.31  5342.0  896.16  5368.9  898.56  5422.3  903.27  5436.7  903.81
#Mann=6,-1,0
  4678.8    0.05       0  4866.5    0.12       0  4984.0    0.07       0
  4996.3    0.12       0  5056.3    0.05       0  5368.9    0.12       0
Bank Sta=4984,4996.3
Exp/Cntr=0.3,0.1

Type RM Length L Ch R = 1,2149,643,643,643
BEGIN DESCRIPTION:
UPSHAW CREEK 4.0
END DESCRIPTION:
XS GIS Cut Line= 3
      2883795.06     10178742.50      2883264.41     10178850.59
      2883114.80     10178928.65
#Sta/Elev= 30
  4599.9  906.50  4619.7  905.76  4647.3  900.86  4660.5  899.79  4727.5  888.49
  4946.2  877.04  4966.7  873.78  4975.2  866.84  4980.9  865.60  4981.4  862.60
  4992.8  862.60  4993.3  865.60  5007.5  869.91  5017.7  870.93  5030.9  869.65
  5038.1  870.74  5058.5  870.46  5068.7  872.36  5076.4  880.45  5081.5  880.31
  5089.1  884.66  5099.3  886.30  5143.6  887.00  5157.3  888.36  5179.4  887.42
  5226.9  888.69  5245.7  889.15  5267.8  892.15  5275.4  891.03  5310.2  893.05
#Mann=5,-1,0
  4599.9    0.05       0  4647.3    0.12       0  4980.9    0.07       0
  4993.3    0.12       0  5226.9    0.05       0
Bank Sta=4980.9,4993.3
Exp/Cntr=0.3,0.1

Type RM Length L Ch R = 1,1506,226,226,226
BEGIN DESCRIPTION:
UPSHAW CREEK 3.0
END DESCRIPTION:
XS GIS Cut Line= 3
      2883255.66     10178253.13      2882963.05     10178470.62
      2882738.84     10178477.12
#Sta/Elev= 30
  4882.4  886.97  4889.7  885.86  4910.5  884.95  4939.7  880.61  4946.0  878.37
  4954.4  877.51  4960.6  872.37  4969.0  869.71  4975.2  863.88  4982.9  861.90
  5004.4  861.48  5004.9  858.48  5016.4  858.48  5016.9  861.48  5025.3  863.69
  5039.9  864.21  5054.5  865.82  5060.7  867.98  5075.3  867.77  5119.1  870.92
  5140.0  871.12  5169.0  873.78  5181.7  875.77  5210.9  877.87  5240.1  882.76
  5254.4  883.92  5274.4  889.25  5324.4  897.48  5404.4  905.75  5471.3  910.31
#Mann=4,-1,0
  4882.4    0.12       0  4982.9    0.05       0  5004.4    0.05       0
  5016.9    0.05       0
Bank Sta=5004.4,5016.9
Exp/Cntr=0.3,0.1

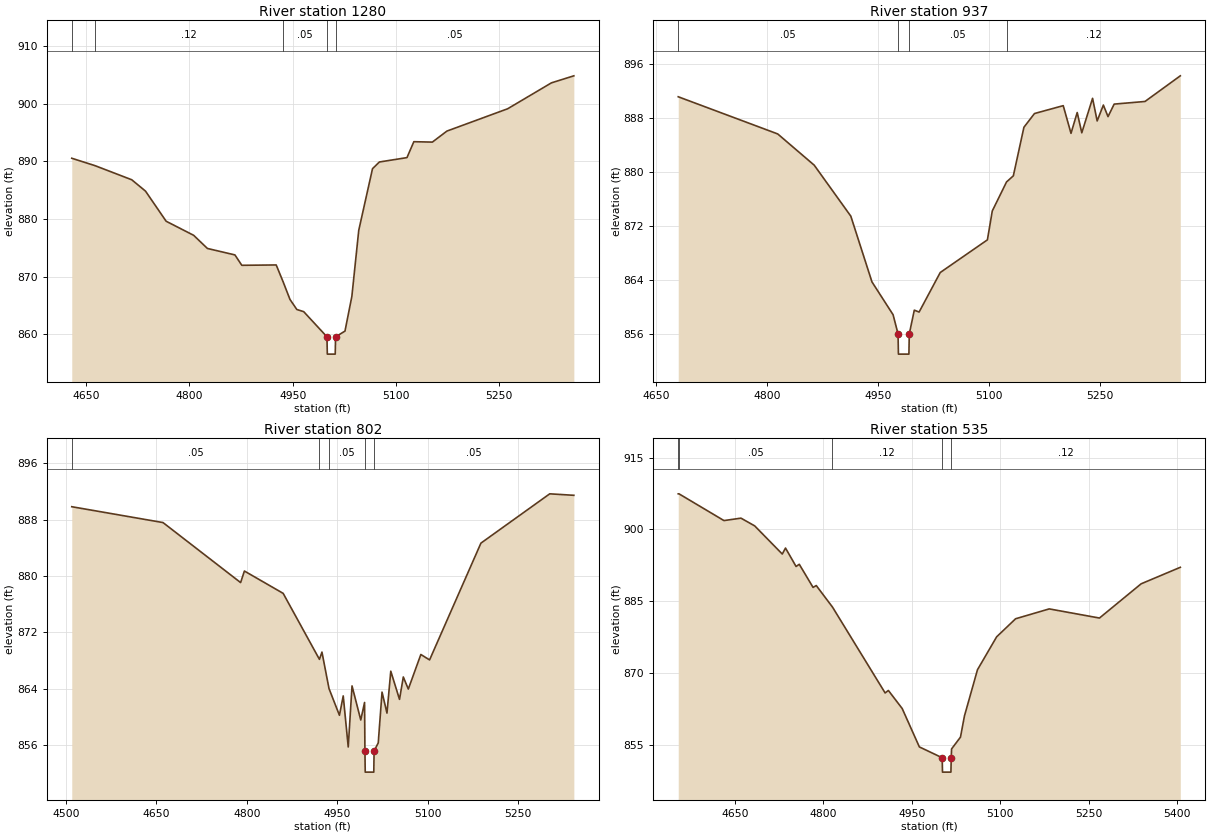
Type RM Length L Ch R = 1,1280,343,343,343
BEGIN DESCRIPTION:
Mapping XS bed25fd0
END DESCRIPTION:
XS GIS Cut Line= 3
      2883352.90     10178188.92      2882832.03     10178195.47
      2882655.17     10178306.82
#Sta/Elev= 30
  4628.9  890.51  4662.6  889.23  4716.1  886.78  4736.1  884.81  4766.1  879.59
  4806.1  877.15  4826.1  874.87  4866.1  873.75  4876.1  871.95  4926.1  872.01
  4936.3  869.05  4946.1  866.04  4956.1  864.29  4966.1  863.91  4999.9  859.55
  5000.4  856.55  5011.9  856.55  5012.4  859.55  5026.1  860.54  5036.1  866.57
  5046.1  878.01  5066.1  888.70  5076.1  889.86  5116.2  890.62  5126.2  893.38
  5153.1  893.31  5174.3  895.22  5262.6  899.09  5326.2  903.58  5358.8  904.80
#Mann=5,-1,0
  4628.9    0.05       0  4662.6    0.12       0  4936.3    0.05       0
  4999.9    0.05       0  5012.4    0.05       0
Bank Sta=4999.9,5012.4
Exp/Cntr=0.3,0.1

Type RM Length L Ch R = 1,937,135,135,135
BEGIN DESCRIPTION:
UPSHAW CREEK 2.0
END DESCRIPTION:
XS GIS Cut Line= 3
      2883388.89     10178179.09      2883054.77     10177779.47
      2882960.25     10177652.35
#Sta/Elev= 30
  4679.6  891.17  4814.2  885.65  4863.6  881.01  4913.1  873.44  4941.7  863.68
  4970.3  858.80  4977.0  855.95  4977.5  852.95  4991.7  852.95  4992.2  855.95
  4999.0  859.48  5005.5  859.20  5034.1  865.07  5097.9  869.92  5104.5  874.21
  5123.8  878.52  5133.0  879.43  5147.3  886.64  5161.6  888.68  5200.5  889.85
  5211.0  885.74  5219.4  888.83  5225.6  885.82  5240.2  890.94  5246.4  887.58
  5254.8  889.94  5261.1  888.22  5269.4  890.08  5311.1  890.47  5358.9  894.28
#Mann=4,-1,0
  4679.6    0.05       0  4977.0    0.03       0  4992.2    0.05       0
  5123.8    0.12       0
Bank Sta=4977,4992.2
Exp/Cntr=0.3,0.1

Type RM Length L Ch R = 1,802,267,267,267
BEGIN DESCRIPTION:
Mapping XS 004f2e45
END DESCRIPTION:
XS GIS Cut Line= 2
      2883552.65     10178208.55      2883045.43     10177547.53
#Sta/Elev= 30
  4509.5  889.85  4660.9  887.60  4789.7  879.08  4796.0  880.72  4860.3  877.55
  4920.5  868.18  4924.7  869.21  4936.4  864.03  4953.7  860.24  4960.0  862.99
  4968.3  855.74  4974.6  864.41  4989.1  859.57  4995.4  862.06  4996.0  855.17
  4996.5  852.17  5010.7  852.17  5011.2  855.17  5018.1  856.32  5024.4  863.53
  5032.6  860.55  5038.9  866.50  5053.4  862.50  5059.7  865.68  5068.0  863.96
  5088.8  868.87  5103.3  868.10  5188.5  884.68  5302.7  891.68  5342.7  891.47
#Mann=5,-1,0
  4509.5    0.05       0  4920.5    0.12       0  4936.4    0.05       0
  4996.0    0.03       0  5011.2    0.05       0
Bank Sta=4996,5011.2
Exp/Cntr=0.3,0.1

Type RM Length L Ch R = 1,535,0,0,0
BEGIN DESCRIPTION:
UPSHAW CREEK 1.0
END DESCRIPTION:
XS GIS Cut Line= 3
      2883719.68     10177740.14      2883175.97     10177501.04
      2882972.88     10177343.81
#Sta/Elev= 30
  4554.1  907.44  4555.4  907.44  4631.6  901.85  4660.4  902.36  4683.7  900.74
  4730.4  894.86  4735.9  896.11  4753.8  892.26  4759.2  892.72  4782.6  887.89
  4788.0  888.28  4815.5  883.78  4904.7  865.84  4910.2  866.36  4933.6  862.59
  4962.7  854.57  5001.4  852.30  5001.9  849.30  5016.2  849.30  5016.7  852.30
  5017.3  854.14  5032.4  856.62  5039.1  861.03  5061.2  870.69  5093.7  877.57
  5125.8  881.34  5182.8  883.40  5267.9  881.49  5338.5  888.64  5404.9  892.09
#Mann=5,-1,0
  4554.1    0.12       0  4555.4    0.05       0  4815.5    0.12       0
  5001.4    0.07       0  5016.7    0.12       0
Bank Sta=5001.4,5016.7
Exp/Cntr=0.3,0.1

Chan Stop Cuts=-1