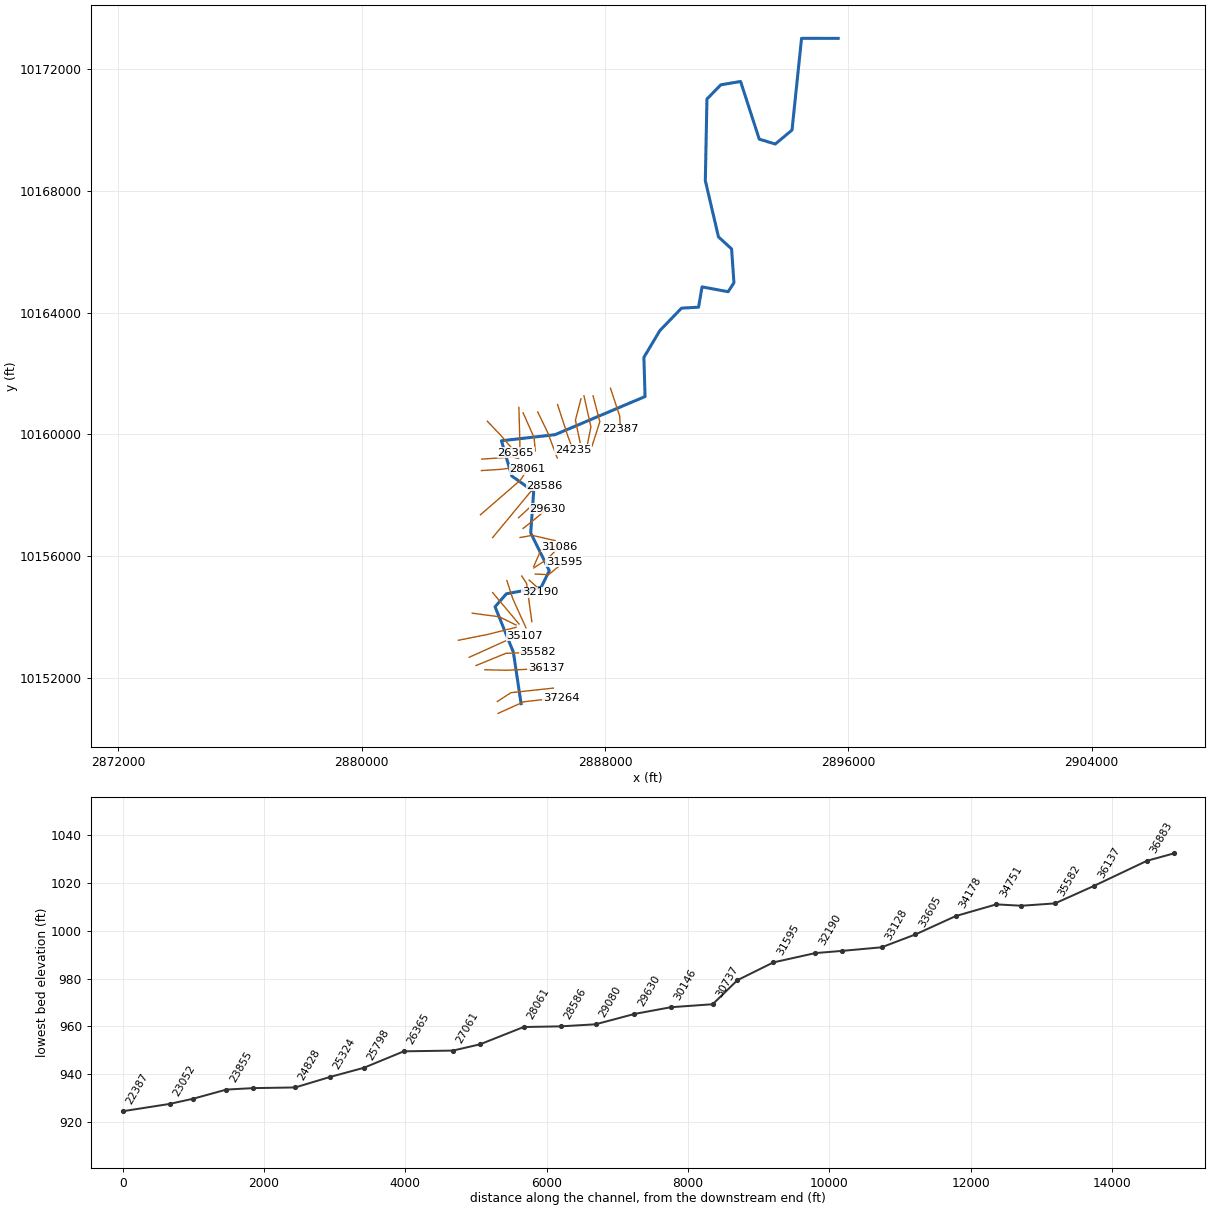
--- WALNUT CREEK.prj (project) ---

Proj Title=WALNUT CREEK Base Level Engineering
Current Plan=p01
Default Exp/Contr=0.3,0.1
English Units
Geom File=g01
Flow File=f01
Plan File=p01
Y Axis Title=Elevation
X Axis Title(PF)=Main Channel Distance
X Axis Title(XS)=Station
BEGIN DESCRIPTION:
WALNUT CREEK
END DESCRIPTION:
DSS Export Rating Curves= 0
DSS Export Rating Curve Sorted= 0
DSS Export Volume Flow Curves= 0
DXF OffsetX= 0
DXF OffsetY= 0
DXF ScaleX= 1
DXF ScaleY= 10

--- WALNUT CREEK.p01 (plan) ---

Plan Title=Multiple Run
Short Identifier=Multiple
Geom File=g01
Flow File=f01
Subcritical Flow
K Sum by GR= 0
Std Step Tol= 0.01
Critical Tol= 0.01
Num of Std Step Trials= 20
Max Error Tol= 0.3
Flow Tol Ratio= 0.001
Split Flow NTrial= 30
Split Flow Tol= 0.02
Split Flow Ratio= 0.02
Log Output Level= 0
Friction Slope Method= 1
Unsteady Friction Slope Method= 2
Unsteady Bridges Friction Slope Method= 1
Parabolic Critical Depth
Global Vel Dist=  1 , 1 , 1
Global Log Level= 0
CheckData=True
Encroach Param= -1, 0, 0, 0
BEGIN DESCRIPTION:
Multiple Run
END DESCRIPTION:

--- WALNUT CREEK.f01 (steady flow) ---

Flow Title=Multiple
Number of Profiles=7
Profile Names=10-year,25-year,50-year,1pct_min,100-year,1pct_plu,500-year
River Rch & RM= WALNUT CREEK,Reach-1,37264
     335     756    1278     707    2137    6452    6335
River Rch & RM= WALNUT CREEK,Reach-1,36137
     530    1228    2107    1180    3565   10765   10818
River Rch & RM= WALNUT CREEK,Reach-1,31595
     579    1349    2319    1302    3932   11874   11982
River Rch & RM= WALNUT CREEK,Reach-1,22387
     593    1383    2380    1337    4038   12196   12320
River Rch & RM= WALNUT CREEK,Reach-1,20056
     651    1525    2631    1481    4474   13511   13704
River Rch & RM= WALNUT CREEK,Reach-1,16972
     670    1571    2713    1528    4615   13938   14155
River Rch & RM= WALNUT CREEK,Reach-1,12930
     684    1607    2775    1565    4725   14268   14504
River Rch & RM= WALNUT CREEK,Reach-1,9357
     703    1652    2855    1611    4864   14688   14947
River Rch & RM= WALNUT CREEK,Reach-1,4307
     707    1664    2876    1623    4900   14799   15065
Boundary for River Rch & Prof#=WALNUT CREEK,Reach-1,1
Up Type=0
Dn Type=3
Dn Slope=0.005
Boundary for River Rch & Prof#=WALNUT CREEK,Reach-1,2
Up Type=0
Dn Type=3
Dn Slope=0.005
Boundary for River Rch & Prof#=WALNUT CREEK,Reach-1,3
Up Type=0
Dn Type=3
Dn Slope=0.005
Boundary for River Rch & Prof#=WALNUT CREEK,Reach-1,4
Up Type=0
Dn Type=3
Dn Slope=0.005
Boundary for River Rch & Prof#=WALNUT CREEK,Reach-1,5
Up Type=0
Dn Type=3
Dn Slope=0.005
Boundary for River Rch & Prof#=WALNUT CREEK,Reach-1,6
Up Type=0
Dn Type=3
Dn Slope=0.005
Boundary for River Rch & Prof#=WALNUT CREEK,Reach-1,7
Up Type=0
Dn Type=3
Dn Slope=0.005

--- WALNUT CREEK.g01 (geometry) ---

Geom Title=Existing Conditions
Program Version=4.10

River Reach=WALNUT CREEK    ,Reach-1
Reach XY= 30
      2885239.25       10151142.       2884985.5       10152836.
      2884383.75       10154326.      2884755.75       10154754.
      2885897.25       10154965.       2886167.5       10155513.
      2885556.25       10156755.      2885653.25       10158116.
       2884932.5       10158628.        2884594.       10159785.
       2886357.5       10159985.      2889315.25       10161239.
      2889276.75       10162527.      2889801.75       10163407.
       2890514.5       10164145.      2891074.25       10164177.
       2891188.5       10164844.        2892046.       10164685.
        2892237.       10164979.        2892160.       10166092.
      2891728.75       10166487.      2891296.25       10168338.
      2891349.75       10171020.      2891805.75       10171487.
        2892456.       10171596.        2893069.       10169701.
        2893596.       10169540.       2894146.5       10169999.
        2894460.       10173015.       2895663.5       10173014.

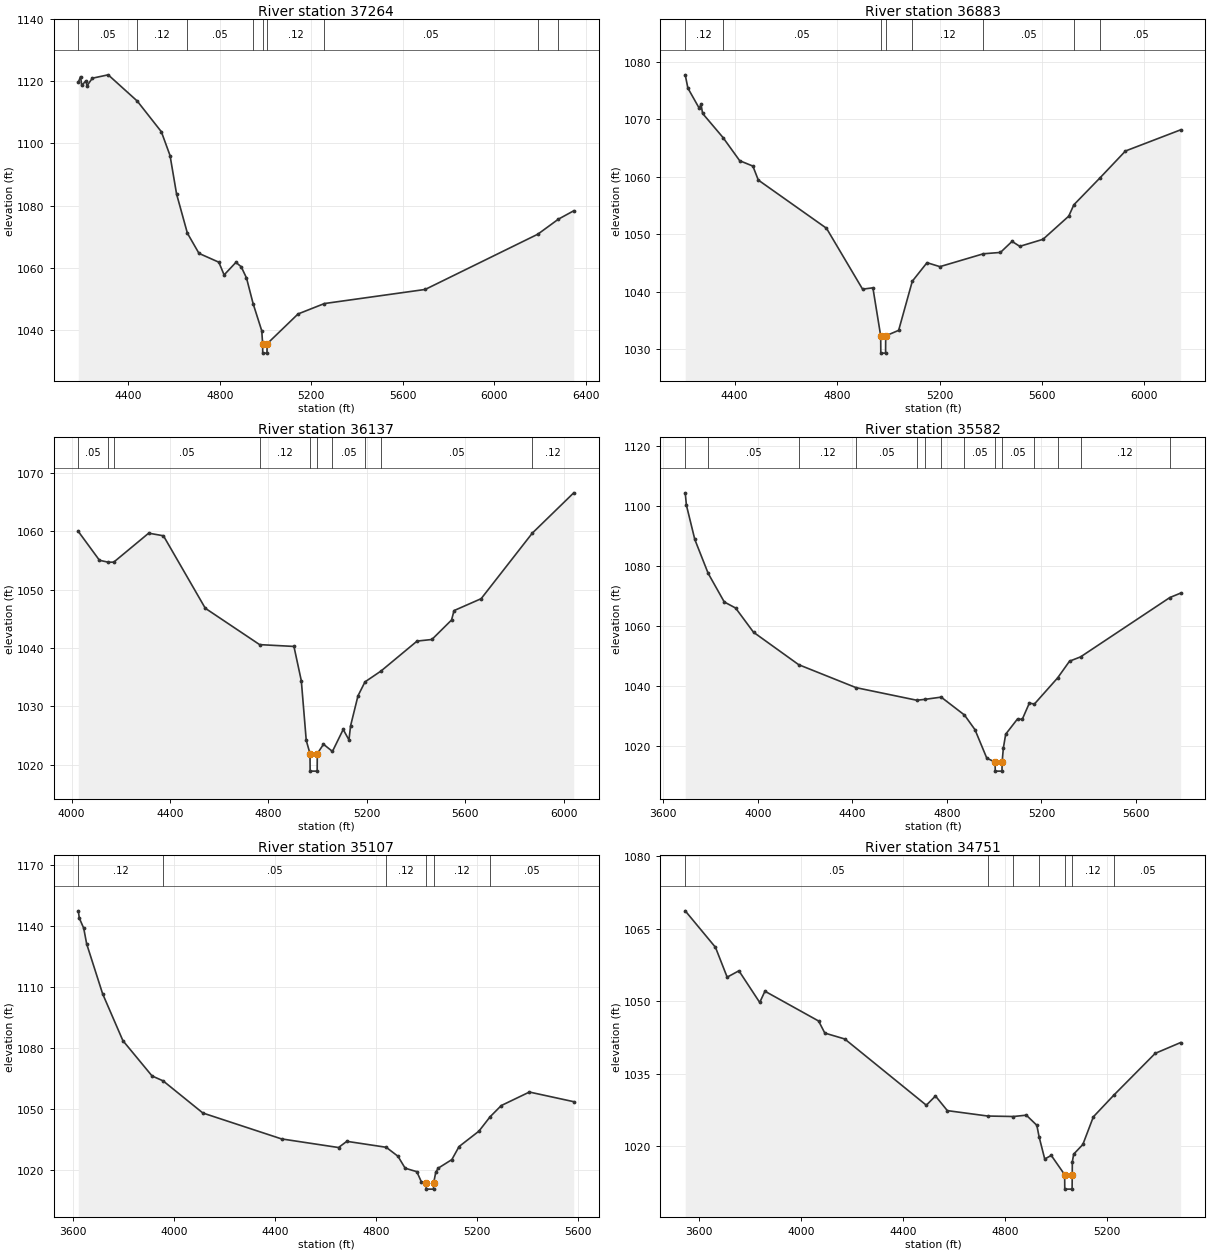
Type RM Length L Ch R = 1 ,37264   ,381,381,381
BEGIN DESCRIPTION:
WALNUT CREEK 70.0
END DESCRIPTION:
XS GIS Cut Line= 3
      2884484.96     10150822.78      2885325.66     10151203.57
      2886561.32     10151341.96
#Sta/Elev= 30
  4181.8 1119.68  4191.4 1121.51  4196.9  1118.7  4214.5 1120.13    4220 1118.59
  4243.1 1121.01  4312.4  1122.1  4439.4 1113.66  4544.9 1103.77  4582.9  1096.1
  4611.5 1083.69  4658.7  1071.1  4709.5 1064.58  4796.3 1061.74  4819.3 1057.64
    4871 1061.69  4894.1 1060.27  4917.2 1056.67  4946.1  1048.4    4984 1039.62
  4987.7 1035.45  4988.2 1032.45  5006.8 1032.45  5007.3 1035.45  5142.7 1045.07
  5257.8 1048.42  5698.4 1052.96    6191 1070.76  6281.3 1075.62  6348.1  1078.3
#Mann= 9 ,-1 , 0
  4181.8     .05       0  4439.4     .12       0  4658.7     .05       0
  4946.1     .12       0  4987.7     .07       0  5007.3     .12       0
  5257.8     .05       0    6191     .12       0  6281.3     .05       0
Bank Sta=4987.7,5007.3
XS Rating Curve= 0 ,0
Exp/Cntr=0.3,0.1

Type RM Length L Ch R = 1 ,36883   ,746,746,746
BEGIN DESCRIPTION:
WALNUT CREEK 69.0
END DESCRIPTION:
XS GIS Cut Line= 3
      2884460.27     10151213.47      2884905.68     10151503.11
      2886299.88     10151653.58
#Sta/Elev= 30
  4207.5 1077.72    4218  1075.4  4261.7 1071.95  4269.3 1072.57  4275.3 1071.01
    4355 1066.82  4420.2 1062.79  4471.6 1061.86  4492.7 1059.43  4758.9 1051.05
  4899.7 1040.47    4940  1040.7  4970.4 1032.35  4970.9 1029.35  4989.5 1029.35
    4990 1032.35  5040.5 1033.31  5093.8 1041.85  5151.2 1045.07  5201.5 1044.38
  5371.5 1046.62  5437.8 1046.85  5483.1 1048.77  5513.3 1047.91  5603.8 1049.13
  5704.4 1053.16  5724.3 1055.13  5827.4 1059.86  5925.7 1064.48  6141.1 1068.16
#Mann= 8 ,-1 , 0
  4207.5     .12       0    4355     .05       0  4970.4     .05       0
    4990     .05       0  5093.8     .12       0  5371.5     .05       0
  5724.3     .12       0  5827.4     .05       0
Bank Sta=4970.4,4990
XS Rating Curve= 0 ,0
Exp/Cntr=0.3,0.1

Type RM Length L Ch R = 1 ,36137   ,555,555,555
BEGIN DESCRIPTION:
WALNUT CREEK 68.0
END DESCRIPTION:
XS GIS Cut Line= 3
      2884049.77     10152256.89      2884772.24     10152240.37
      2886061.54     10152301.35
#Sta/Elev= 30
  4027.4    1060  4113.3 1055.05  4149.1 1054.72  4171.4 1054.73  4313.4  1059.7
  4373.4 1059.25  4543.4 1046.82  4764.3 1040.58  4903.7 1040.27  4933.7 1034.38
  4953.7 1024.15    4969 1021.88  4969.5 1018.88  4998.1 1018.88  4998.6 1021.88
  5023.8 1023.49  5060.2 1022.26  5103.9 1026.03  5127.3 1024.23  5133.9 1026.65
    5164  1031.8  5192.5 1034.19  5257.5 1036.05  5404.2 1041.19  5464.3 1041.46
  5544.2  1044.8  5554.4 1046.42  5664.5 1048.46  5872.3  1059.7  6040.8 1066.62
#Mann= 10 ,-1 , 0
  4027.4     .05       0  4149.1     .12       0  4171.4     .05       0
  4764.3     .12       0    4969     .07       0  4998.6     .12       0
  5060.2     .05       0  5192.5     .12       0  5257.5     .05       0
  5872.3     .12       0
Bank Sta=4969,4998.6
XS Rating Curve= 0 ,0
Exp/Cntr=0.3,0.1

Type RM Length L Ch R = 1 ,35582   ,475,475,475
BEGIN DESCRIPTION:
WALNUT CREEK 67.0
END DESCRIPTION:
XS GIS Cut Line= 3
      2883758.08     10152395.36      2884737.18     10152795.91
      2885775.66     10152835.47
#Sta/Elev= 30
  3692.3 1104.39  3697.3 1100.29  3732.9 1088.82  3789.4 1077.52  3857.6 1067.96
  3905.6 1065.94  3981.4 1057.86  4172.8 1047.02  4415.6 1039.36  4672.5 1035.16
  4705.4 1035.44  4775.7  1036.2  4874.3 1030.23  4918.8 1025.34  4968.8 1015.84
  5004.1  1014.5  5004.6  1011.5  5033.2  1011.5  5033.7  1014.5  5038.9  1019.2
  5048.9 1023.84  5098.9 1028.92  5118.9 1028.77    5149 1034.22  5170.2 1033.88
  5268.8 1042.63  5319.1  1048.2  5365.7 1049.63  5743.9 1069.45  5789.4 1070.92
#Mann= 14 ,-1 , 0
  3692.3     .12       0  3789.4     .05       0  4172.8     .12       0
  4415.6     .05       0  4672.5     .12       0  4705.4     .05       0
  4775.7     .12       0  4874.3     .05       0  5004.1     .03       0
  5033.7     .05       0  5170.2     .12       0  5268.8     .05       0
  5365.7     .12       0  5743.9     .05       0
Bank Sta=5004.1,5033.7
XS Rating Curve= 0 ,0
Exp/Cntr=0.3,0.1

Type RM Length L Ch R = 1 ,35107   ,356,356,356
BEGIN DESCRIPTION:
WALNUT CREEK 66.0
END DESCRIPTION:
XS GIS Cut Line= 3
      2883535.53     10152667.34      2884949.83     10153305.26
      2885355.29     10153379.43
#Sta/Elev= 30
  3620.8  1147.5  3624.6 1143.96  3642.2 1138.95  3653.9 1131.23  3717.1 1106.68
  3797.5  1083.6  3913.1 1066.22  3956.9  1063.8  4114.6 1047.97  4426.3 1035.23
  4652.2 1030.99  4685.1 1034.04  4841.2 1031.11  4887.7  1026.7  4916.3 1020.81
  4962.6 1019.09  4980.2 1014.18  4999.5 1013.51    5000 1010.51  5028.7 1010.51
  5029.2 1013.51  5037.5 1018.73  5047.1 1020.81  5101.4 1025.05    5130 1031.47
  5208.8 1039.06  5253.1 1046.14  5297.3 1051.65  5408.7  1058.3  5584.5 1053.55
#Mann= 6 ,-1 , 0
  3620.8     .12       0  3956.9     .05       0  4841.2     .12       0
  4999.5     .07       0  5029.2     .12       0  5253.1     .05       0
Bank Sta=4999.5,5029.2
XS Rating Curve= 0 ,0
Exp/Cntr=0.3,0.1

Type RM Length L Ch R = 1 ,34751   ,573,573,573
BEGIN DESCRIPTION:
WALNUT CREEK 65.0
END DESCRIPTION:
XS GIS Cut Line= 3
      2883179.45     10153226.13      2884118.42      10153412.6
      2885072.05     10153651.06
#Sta/Elev= 30
  3546.8 1068.73  3665.3 1061.17  3711.1 1054.99  3757.1 1056.31  3838.6 1049.75
    3859 1052.08  4069.2 1045.91  4093.5 1043.41  4171.5 1042.19  4491.1 1028.47
  4526.9 1030.38  4573.4 1027.35  4731.5 1026.23  4832.2 1026.13  4882.7 1026.41
  4923.9 1024.31  4932.9 1021.89  4954.8 1017.33  4980.4 1018.07  5032.8 1014.09
  5033.3 1011.09    5062 1011.09  5062.5 1014.09  5062.9 1016.75  5068.2 1018.34
  5104.1 1020.34  5145.3 1026.07  5226.4 1030.61  5387.5 1039.21  5487.1 1041.45
#Mann= 7 ,-1 , 0
  3546.8     .05       0  4731.5     .12       0  4832.2     .05       0
  4932.9     .12       0  5032.8     .07       0  5062.5     .12       0
  5226.4     .05       0
Bank Sta=5032.8,5062.5
XS Rating Curve= 0 ,0
Exp/Cntr=0.3,0.1

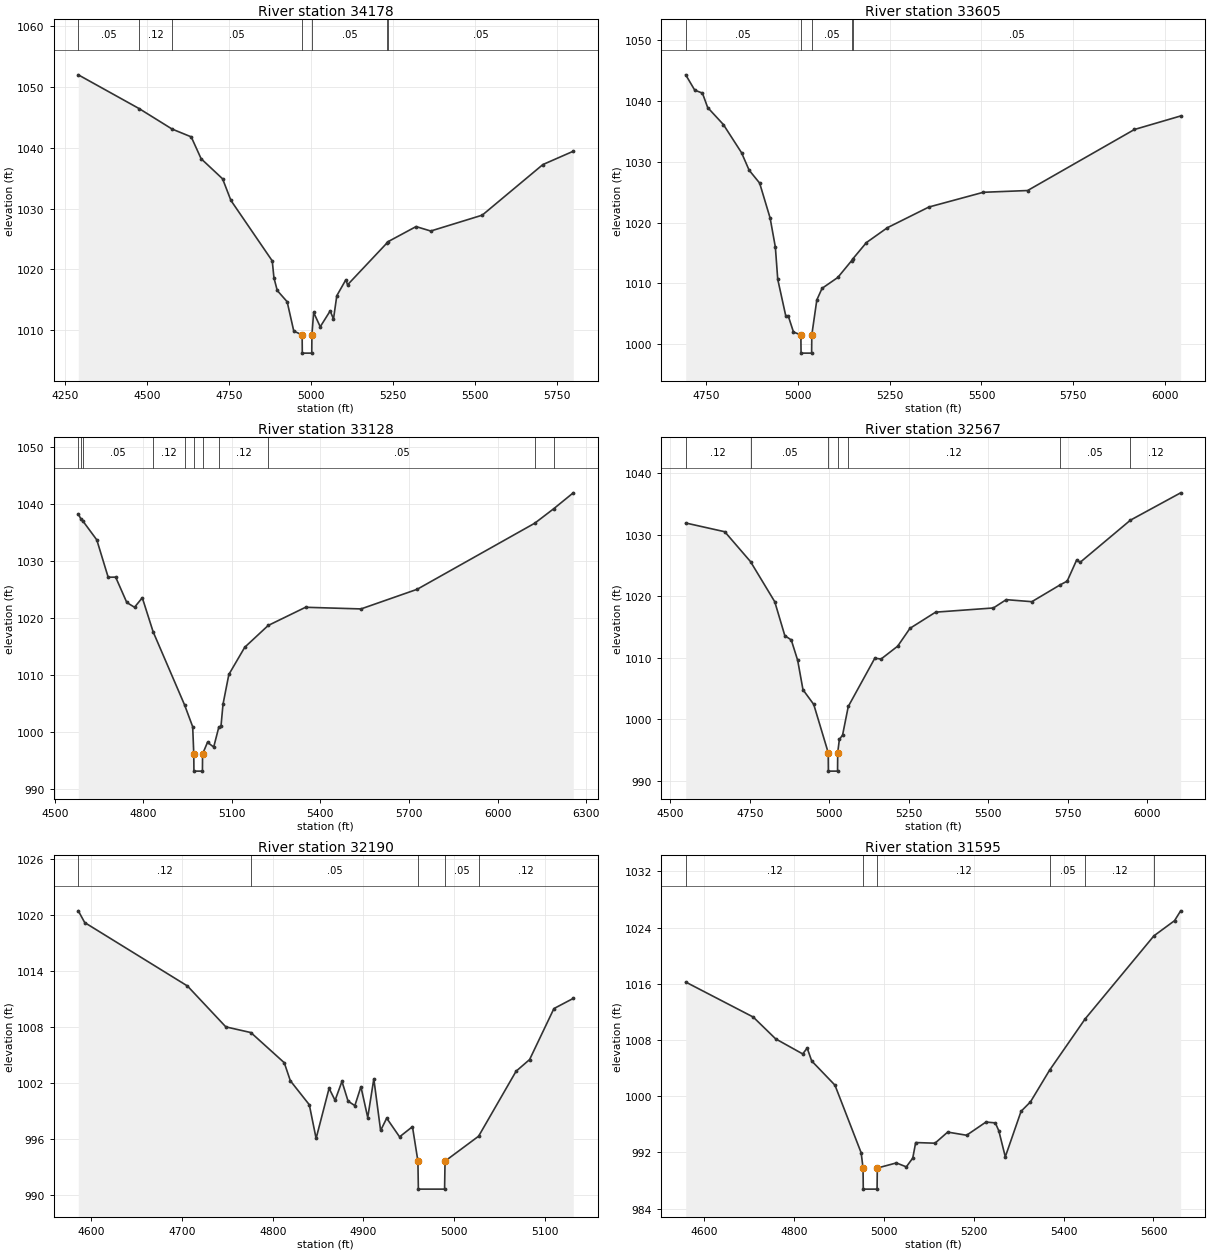
Type RM Length L Ch R = 1 ,34178   ,573,573,573
BEGIN DESCRIPTION:
WALNUT CREEK 64.0
END DESCRIPTION:
XS GIS Cut Line= 3
      2883634.42     10154116.26      2884524.54     10153997.58
      2885072.11     10153726.26
#Sta/Elev= 30
  4291.3 1052.01  4477.2 1046.44  4577.4 1043.08  4635.6  1041.8  4665.8  1038.2
  4731.3 1034.89  4756.6 1031.34  4882.7 1021.38  4887.8 1018.61  4897.9 1016.51
  4928.1 1014.66  4948.3 1009.83  4973.8  1009.2  4974.3  1006.2  5003.1  1006.2
  5003.6  1009.2  5008.9 1012.89    5029 1010.54  5059.3 1013.15  5069.4 1011.82
  5079.5 1015.65  5107.1 1018.28  5112.2 1017.44  5232.6 1024.34  5234.5 1024.51
  5321.1 1027.03  5365.9  1026.3  5522.9 1028.91  5707.8 1037.24  5800.4 1039.43
#Mann= 7 ,-1 , 0
  4291.3     .05       0  4477.2     .12       0  4577.4     .05       0
  4973.8     .05       0  5003.6     .05       0  5232.6     .12       0
  5234.5     .05       0
Bank Sta=4973.8,5003.6
XS Rating Curve= 0 ,0
Exp/Cntr=0.3,0.1

Type RM Length L Ch R = 1 ,33605   ,477,477,477
BEGIN DESCRIPTION:
WALNUT CREEK 63.0
END DESCRIPTION:
XS GIS Cut Line= 3
        2884302.     10154793.76      2884623.45     10154412.97
      2885171.52     10153761.21
#Sta/Elev= 30
  4693.4 1044.34  4718.1 1041.81    4739 1041.33  4753.3 1038.95  4796.1 1036.15
  4845.6 1031.51  4866.4 1028.62    4895  1026.5  4923.6 1020.74  4937.9 1015.95
  4944.4 1010.64  4966.5 1004.55    4973 1004.61  4987.3 1001.95  5007.5 1001.47
    5008  998.47  5036.8  998.47  5037.3 1001.47    5051 1007.24  5065.3 1009.15
  5108.2 1010.94  5146.2 1013.73  5148.3 1013.94  5186.2 1016.69  5243.4 1019.14
  5356.6 1022.55  5505.1 1024.98  5625.9 1025.27  5917.2 1035.33  6043.3 1037.56
#Mann= 5 ,-1 , 0
  4693.4     .05       0  5007.5     .05       0  5037.3     .05       0
  5146.2     .12       0  5148.3     .05       0
Bank Sta=5007.5,5037.3
XS Rating Curve= 0 ,0
Exp/Cntr=0.3,0.1

Type RM Length L Ch R = 1 ,33128   ,561,561,561
BEGIN DESCRIPTION:
WALNUT CREEK 62.0
END DESCRIPTION:
XS GIS Cut Line= 3
      2884771.81     10155189.34      2884964.66     10154595.94
      2885399.51      10153637.3
#Sta/Elev= 30
  4579.8 1038.16  4587.9 1037.38  4595.9  1036.9  4642.5 1033.63    4681 1027.09
  4706.4  1027.1  4744.1 1022.66  4770.3 1021.82  4796.6 1023.49  4833.4 1017.51
  4939.7 1004.72  4967.3 1000.88    4971   996.1  4971.5   993.1  5000.3   993.1
  5000.8   996.1  5017.5  998.15  5038.5  997.32  5055.8 1000.81  5063.1 1000.93
    5070 1004.82  5089.8 1010.04  5143.6 1014.81    5223 1018.63  5349.6 1021.82
  5537.4 1021.53  5727.6 1024.97  6126.1 1036.56  6191.2 1039.13  6256.4 1041.88
#Mann= 11 ,-1 , 0
  4579.8     .05       0  4587.9     .12       0  4595.9     .05       0
  4833.4     .12       0  4939.7     .05       0    4971     .05       0
  5000.8     .05       0  5055.8     .12       0    5223     .05       0
  6126.1     .12       0  6191.2     .05       0
Bank Sta=4971,5000.8
XS Rating Curve= 0 ,0
Exp/Cntr=0.3,0.1

Type RM Length L Ch R = 1 ,32567   ,377,377,377
BEGIN DESCRIPTION:
WALNUT CREEK 61.0
END DESCRIPTION:
XS GIS Cut Line= 3
      2885261.35     10155337.74      2885419.61      10155095.4
       2885592.7     10153839.31
#Sta/Elev= 30
  4548.1 1031.89    4671 1030.47    4752 1025.62  4828.3  1019.1    4860 1013.59
  4880.2  1012.9  4900.4 1009.59  4917.1 1004.81  4950.9 1002.43  4996.5  994.59
    4997  991.59  5025.9  991.59  5026.4  994.59  5031.6  996.74  5041.7  997.45
  5059.6 1002.09  5143.1 1009.93  5162.9  1009.8    5215 1011.88  5253.7 1014.78
  5334.5 1017.41  5516.2 1018.09  5556.6 1019.44  5637.3 1019.11  5725.6 1021.82
  5748.4 1022.45  5778.6 1025.92  5788.7 1025.48  5947.4 1032.35  6105.5 1036.79
#Mann= 7 ,-1 , 0
  4548.1     .12       0    4752     .05       0  4996.5     .05       0
  5026.4     .05       0  5059.6     .12       0  5725.6     .05       0
  5947.4     .12       0
Bank Sta=4996.5,5026.4
XS Rating Curve= 0 ,0
Exp/Cntr=0.3,0.1

Type RM Length L Ch R = 1 ,32190   ,595,595,595
BEGIN DESCRIPTION:
WALNUT CREEK 60.0
END DESCRIPTION:
XS GIS Cut Line= 3
      2885505.71     10155203.09       2885815.5       10154928.
      2885855.69     10154803.11
#Sta/Elev= 30
  4585.7 1020.48  4592.8 1019.22    4706 1012.43  4748.3 1008.05  4775.9 1007.44
  4812.7 1004.21  4819.4 1002.28  4840.3  999.71  4847.8   996.1  4862.1 1001.47
  4868.7 1000.18  4876.3 1002.21    4883  1000.1  4890.5  999.61  4897.2 1001.64
  4904.7  998.34  4911.4 1002.48  4918.9  996.95  4925.6  998.27  4939.8  996.27
    4954  997.36    4960  993.67  4960.5  990.67  4989.4  990.67  4989.9  993.67
  5026.9  996.34  5068.2  1003.3  5083.1 1004.55  5109.9 1010.01  5131.2  1011.1
#Mann= 5 ,-1 , 0
  4585.7     .12       0  4775.9     .05       0    4960     .05       0
  4989.9     .05       0  5026.9     .12       0
Bank Sta=4960,4989.9
XS Rating Curve= 0 ,0
Exp/Cntr=0.3,0.1

Type RM Length L Ch R = 1 ,31595   ,509,509,509
BEGIN DESCRIPTION:
WALNUT CREEK 59.0
END DESCRIPTION:
XS GIS Cut Line= 3
      2885705.66     10155403.11        2886146.       10155383.
      2886655.68     10155803.11
#Sta/Elev= 30
  4559.2 1016.24  4709.4 1011.26  4759.4 1008.15  4819.5 1006.01  4829.5 1006.84
  4839.5 1005.01  4891.3 1001.56  4949.6  991.93  4953.8  989.76  4954.3  986.76
    4985  986.76  4985.5  989.76  5027.9  990.49  5050.1  989.93  5064.4  991.18
  5070.9  993.39  5113.9   993.3  5142.1  994.88  5184.2  994.43  5227.3  996.31
  5248.1  996.19  5255.9  995.06  5270.3  991.36  5305.4  997.84  5326.3  999.18
  5368.7 1003.68  5447.9 1010.99    5601 1022.82  5646.9 1024.98  5660.5 1026.38
#Mann= 6 ,-1 , 0
  4559.2     .12       0  4953.8     .07       0  4985.5     .12       0
  5368.7     .05       0  5447.9     .12       0    5601     .05       0
Bank Sta=4953.8,4985.5
XS Rating Curve= 0 ,0
Exp/Cntr=0.3,0.1

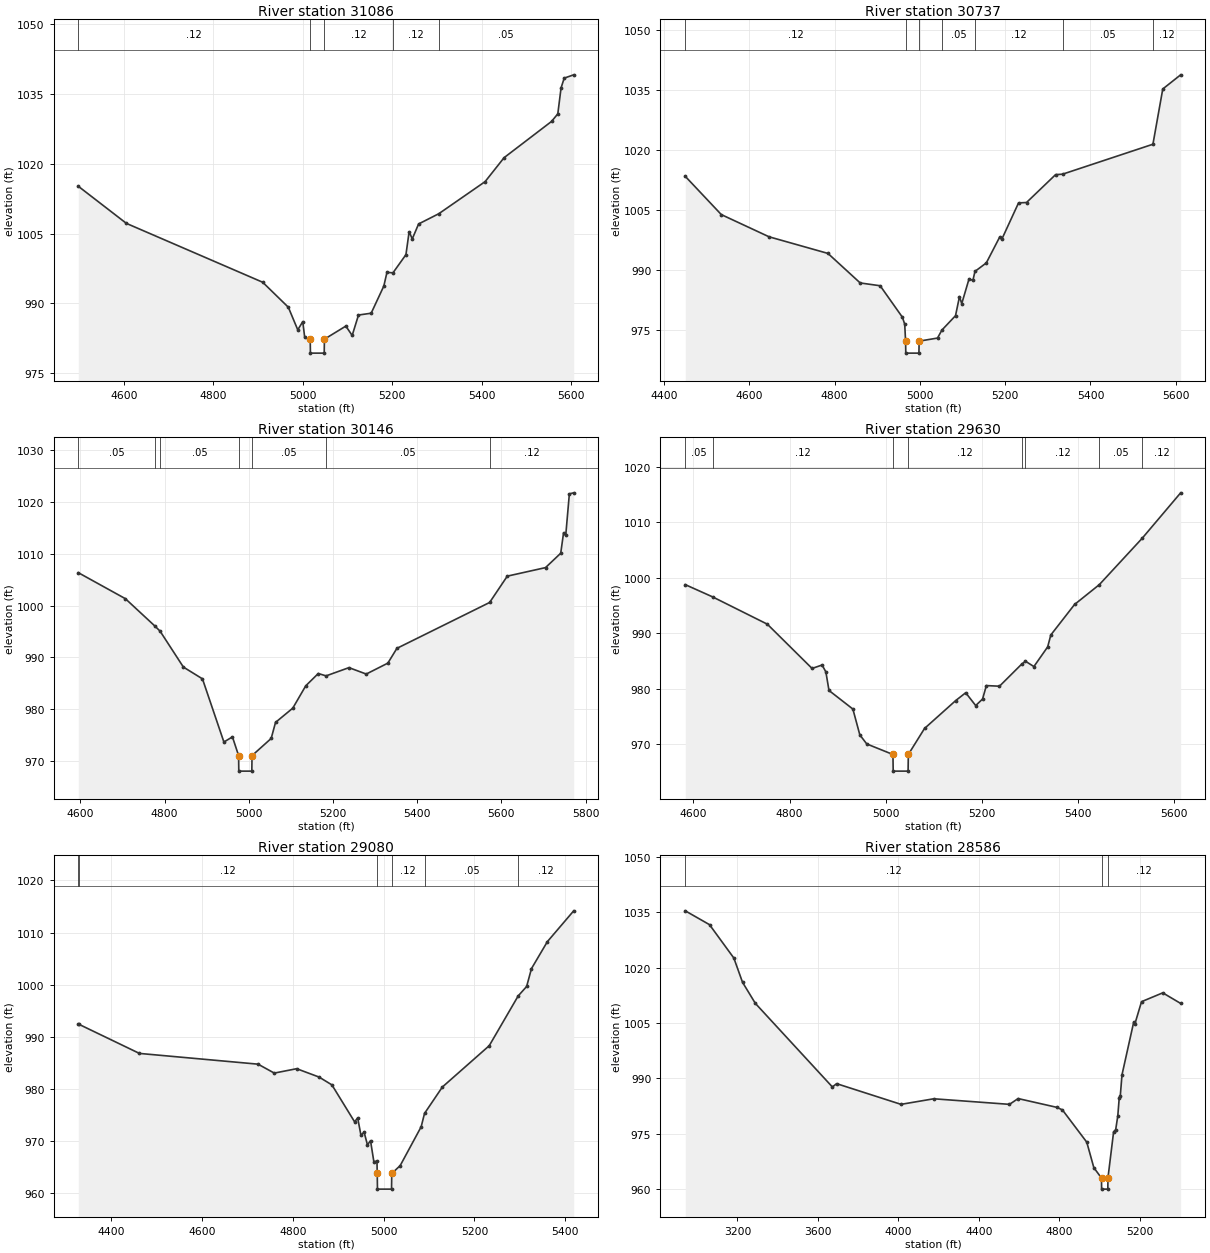
Type RM Length L Ch R = 1 ,31086   ,349,349,349
BEGIN DESCRIPTION:
WALNUT CREEK 58.0
END DESCRIPTION:
XS GIS Cut Line= 3
      2885655.66     10155603.09      2886075.75       10155877.
      2886505.67      10156303.1
#Sta/Elev= 30
  4498.5 1015.16    4606 1007.18  4910.4  994.53  4967.7  989.16  4988.8   984.3
    5000  986.06  5004.3  982.67  5016.6  982.29  5017.1  979.29  5047.9  979.29
  5048.4  982.29  5096.2   985.1  5110.4  983.09  5124.5  987.48  5152.8  987.87
  5181.1  993.71  5188.1  996.66  5201.5  996.55  5230.5 1000.46  5237.6 1005.37
  5244.7 1003.86  5258.8 1007.06  5303.9 1009.26  5407.4 1016.16  5449.8 1021.31
  5555.8  1029.1  5569.8 1030.73  5577.1 1036.31  5584.1 1038.41  5605.3 1039.12
#Mann= 5 ,-1 , 0
  4498.5     .12       0  5016.6     .07       0  5048.4     .12       0
  5201.5     .12       0  5303.9     .05       0
Bank Sta=5016.6,5048.4
XS Rating Curve= 0 ,0
Exp/Cntr=0.3,0.1

Type RM Length L Ch R = 1 ,30737   ,591,591,591
BEGIN DESCRIPTION:
WALNUT CREEK 57.0
END DESCRIPTION:
XS GIS Cut Line= 3
       2885655.7     10155653.16       2885876.5       10156157.
       2886455.7     10156353.12
#Sta/Elev= 30
  4449.9 1013.47  4534.4  1003.9  4646.4  998.34  4784.5  994.18  4860.1  986.79
  4906.9  986.09  4959.1  978.21  4964.5  976.46  4966.5  972.23    4967  969.23
  4997.8  969.23  4998.3  972.23  5041.4     973  5051.7     975  5083.6   978.6
  5092.9  983.37  5098.2  981.61  5115.3   987.8  5124.4  987.43  5129.2  989.68
  5155.8   991.8  5187.2  998.28  5192.5  997.81  5231.4 1006.82  5250.1 1006.92
  5318.2 1013.89  5334.7 1014.01  5546.5  1021.5  5569.6 1035.33  5611.5 1038.87
#Mann= 7 ,-1 , 0
  4449.9     .12       0  4966.5     .07       0  4998.3     .12       0
  5051.7     .05       0  5129.2     .12       0  5334.7     .05       0
  5546.5     .12       0
Bank Sta=4966.5,4998.3
XS Rating Curve= 0 ,0
Exp/Cntr=0.3,0.1

Type RM Length L Ch R = 1 ,30146   ,516,516,516
BEGIN DESCRIPTION:
WALNUT CREEK 56.0
END DESCRIPTION:
XS GIS Cut Line= 3
      2885205.67     10156603.11      2885603.75       10156676.
      2886355.73      10156503.1
#Sta/Elev= 30
  4595.3 1006.35  4707.1 1001.32  4777.3  996.02  4789.5  995.04  4844.8   988.1
  4890.1  985.82    4941  973.61  4961.3   974.6  4975.9  970.98  4976.4  967.98
  5007.3  967.98  5007.8  970.98  5053.3   974.3  5063.6   977.4  5104.6  980.16
  5135.4  984.48  5165.1  986.85  5183.7   986.4    5238  987.99    5279  986.75
  5330.3  988.86  5351.8  991.72    5572 1000.59  5613.9 1005.68  5704.7 1007.33
  5740.8 1010.11  5747.6 1014.09  5752.7 1013.55  5761.3 1021.59  5771.6 1021.79
#Mann= 7 ,-1 , 0
  4595.3     .05       0  4777.3     .12       0  4789.5     .05       0
  4975.9     .07       0  5007.8     .05       0  5183.7     .05       0
    5572     .12       0
Bank Sta=4975.9,5007.8
XS Rating Curve= 0 ,0
Exp/Cntr=0.3,0.1

Type RM Length L Ch R = 1 ,29630   ,550,550,550
BEGIN DESCRIPTION:
WALNUT CREEK 55.0
END DESCRIPTION:
XS GIS Cut Line= 3
      2885305.68     10156903.11       2885633.5       10157161.
      2886105.71     10157553.13
#Sta/Elev= 30
  4582.9  998.78  4639.6  996.58  4753.7  991.65  4846.8  983.67  4867.6  984.29
  4875.5  983.05    4882   979.7  4931.7  976.35  4946.2  971.69  4960.6  970.06
  5015.1  968.16  5015.6  965.16  5046.6  965.16  5047.1  968.16  5080.8  972.85
  5145.7  977.88  5166.5  979.29  5187.3  976.98  5201.6  978.16  5209.5  980.58
  5236.8  980.47  5282.9  984.44  5290.9  984.97  5308.4  984.01  5337.1  987.56
  5343.6   989.7    5393   995.2  5444.6  998.78  5533.6 1007.12  5613.8 1015.33
#Mann= 8 ,-1 , 0
  4582.9     .05       0  4639.6     .12       0  5015.1     .07       0
  5047.1     .12       0  5282.9     .05       0  5290.9     .12       0
  5444.6     .05       0  5533.6     .12       0
Bank Sta=5015.1,5047.1
XS Rating Curve= 0 ,0
Exp/Cntr=0.3,0.1

Type RM Length L Ch R = 1 ,29080   ,494,494,494
BEGIN DESCRIPTION:
WALNUT CREEK 54.0
END DESCRIPTION:
XS GIS Cut Line= 3
      2885155.69     10157253.12       2885650.5       10157709.
      2886055.69     10157603.11
#Sta/Elev= 30
  4327.2  992.44  4327.9  992.44  4461.9  986.83  4723.3  984.77    4759  983.06
  4808.4   983.9  4857.7   982.3    4886   980.8    4936  973.72  4942.8  974.47
  4950.1  971.11  4956.9  971.77  4964.3   969.3  4971.1   970.1  4978.5  966.05
  4985.3  966.21  4985.9  963.82  4986.4  960.82  5017.4  960.82  5017.9  963.82
  5036.4  965.32  5082.7  972.77  5090.1  975.33  5129.4  980.39  5232.7  988.31
  5296.5  997.85  5315.1  999.66  5325.8 1003.09  5360.7 1008.24  5418.8 1014.16
#Mann= 6 ,-1 , 0
  4327.2     .05       0  4327.9     .12       0  4985.9     .07       0
  5017.9     .12       0  5090.1     .05       0  5296.5     .12       0
Bank Sta=4985.9,5017.9
XS Rating Curve= 0 ,0
Exp/Cntr=0.3,0.1

Type RM Length L Ch R = 1 ,28586   ,525,525,525
BEGIN DESCRIPTION:
WALNUT CREEK 53.0
END DESCRIPTION:
XS GIS Cut Line= 3
       2884305.7     10156603.13        2885618.       10158190.
      2886005.64      10158303.1
#Sta/Elev= 30
  2940.8 1035.43  3061.3 1031.68  3182.4 1022.62  3225.4 1016.06  3289.2 1010.34
  3672.2  987.67  3693.4  988.56  4013.5  982.95  4176.3  984.46  4552.8  982.95
  4595.8  984.52  4787.2  982.15  4815.9  981.45  4937.1  972.69  4972.2  965.78
  5010.3  962.96  5010.8  959.96  5041.8  959.96  5042.3  962.96  5070.5  975.49
  5080.9  976.11  5091.3   979.8  5098.5  984.75  5103.7  985.24  5112.2  990.96
  5170.6  1005.3  5175.8 1004.68  5209.3 1010.79  5314.9 1013.19  5403.8 1010.32
#Mann= 3 ,-1 , 0
  2940.8     .12       0  5010.3     .07       0  5042.3     .12       0
Bank Sta=5010.3,5042.3
XS Rating Curve= 0 ,0
Exp/Cntr=0.3,0.1

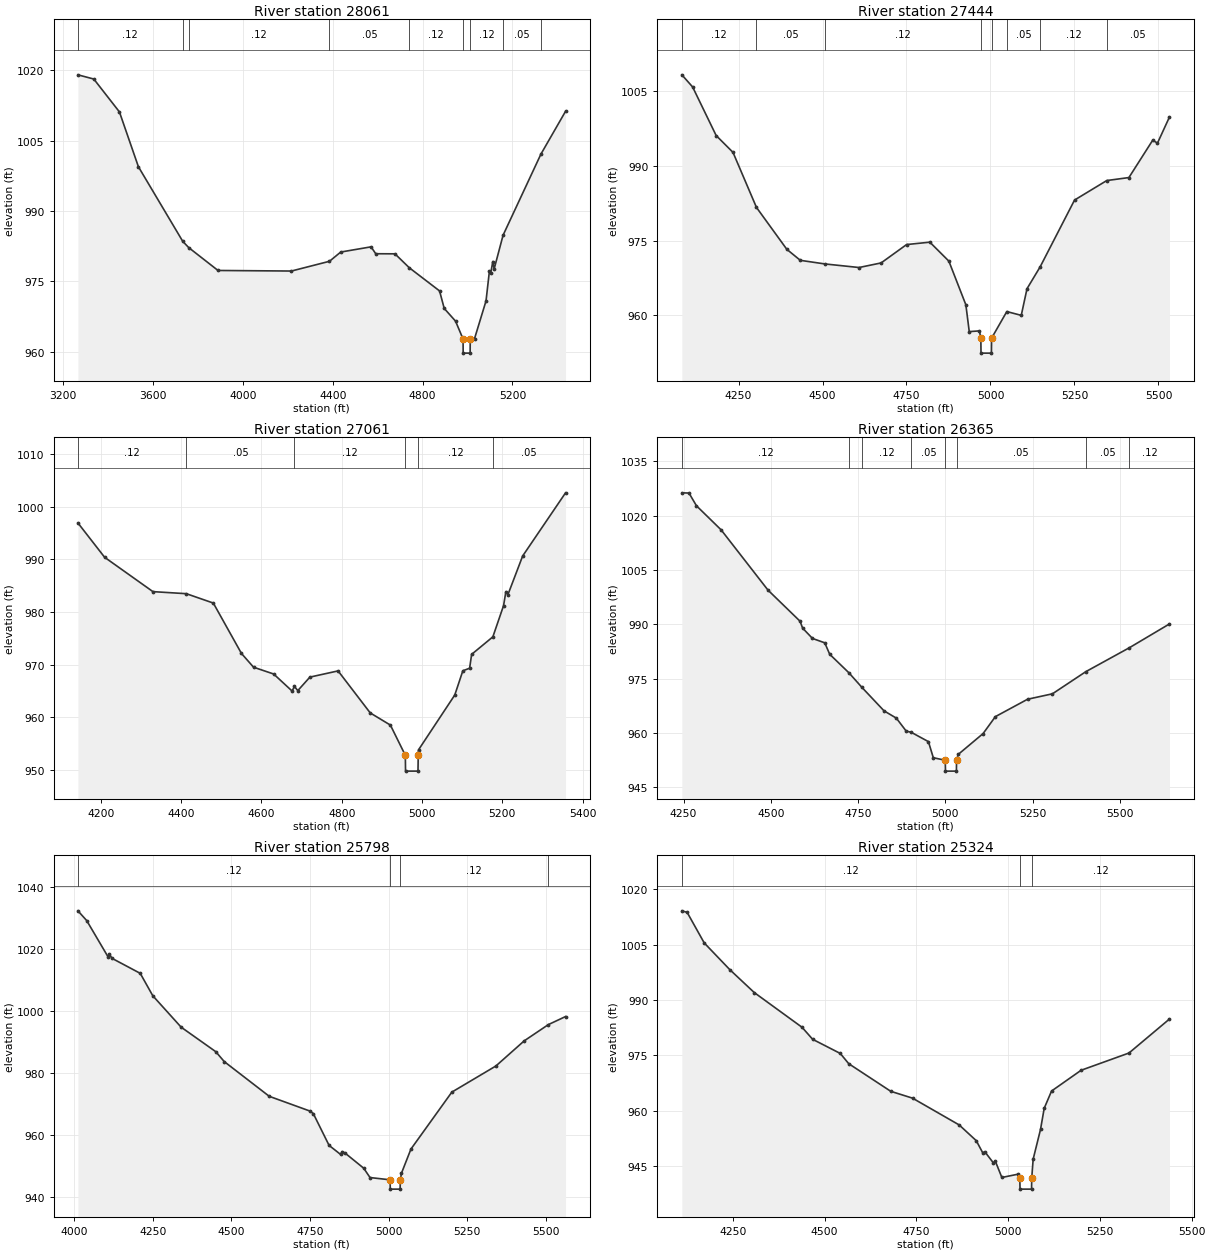
Type RM Length L Ch R = 1 ,28061   ,617,617,617
BEGIN DESCRIPTION:
WALNUT CREEK 52.0
END DESCRIPTION:
XS GIS Cut Line= 3
      2883905.71     10157353.13      2885215.75       10158489.
      2885455.71     10158853.15
#Sta/Elev= 30
  3266.1 1019.04  3336.8 1018.14  3450.8 1011.13  3535.3  999.43  3732.5  983.53
  3759.1  982.19  3889.5  977.31  4216.3  977.19  4385.6  979.27  4435.6  981.24
  4570.5  982.35  4591.4  980.88  4676.9  980.86  4740.7  977.89  4875.4  972.95
  4896.2  969.21  4946.6   966.5    4980  962.68  4980.5  959.68  5011.5  959.68
    5012  962.68    5031  962.76  5082.2  970.82  5097.3  977.19  5103.3  976.79
  5112.4  979.22  5118.4  977.64  5158.1  984.83  5326.5 1002.13  5436.1 1011.26
#Mann= 9 ,-1 , 0
  3266.1     .12       0  3732.5     .05       0  3759.1     .12       0
  4385.6     .05       0  4740.7     .12       0    4980     .07       0
    5012     .12       0  5158.1     .05       0  5326.5     .12       0
Bank Sta=4980,5012
XS Rating Curve= 0 ,0
Exp/Cntr=0.3,0.1

Type RM Length L Ch R = 1 ,27444   ,383,383,383
BEGIN DESCRIPTION:
WALNUT CREEK 51.0
END DESCRIPTION:
XS GIS Cut Line= 3
      2883933.77     10158804.99      2884589.65     10158846.31
      2885375.17      10158963.5
#Sta/Elev= 30
  4081.4 1008.21  4113.4 1005.78  4183.5  996.04  4233.6  992.67  4303.5  981.63
  4393.9  973.23    4434  971.03  4506.6  970.31  4608.8  969.59  4674.5  970.51
  4750.3  974.19  4819.5  974.67  4876.1  970.87  4926.7  962.12  4936.8  956.74
  4967.1  956.89  4971.3  955.43  4971.8  952.43  5002.8  952.43  5003.3  955.43
  5048.6  960.76  5091.6     960  5108.7  965.34  5147.7  969.71  5250.2  983.11
  5346.1  987.02    5412  987.62  5482.8   995.1  5497.1  994.53  5532.8  999.77
#Mann= 8 ,-1 , 0
  4081.4     .12       0  4303.5     .05       0  4506.6     .12       0
  4971.3     .07       0  5003.3     .12       0  5048.6     .05       0
  5147.7     .12       0  5346.1     .05       0
Bank Sta=4971.3,5003.3
XS Rating Curve= 0 ,0
Exp/Cntr=0.3,0.1

Type RM Length L Ch R = 1 ,27061   ,696,696,696
BEGIN DESCRIPTION:
WALNUT CREEK 50.0
END DESCRIPTION:
XS GIS Cut Line= 3
      2883949.31     10159181.98      2884960.83     10159250.58
      2885155.68     10159203.11
#Sta/Elev= 30
    4143  996.92  4209.5   990.4  4329.8  983.88  4412.9  983.49  4480.2  981.71
  4550.3  972.14  4580.4  969.53  4630.5  968.24  4676.3  965.01  4682.3  965.87
  4690.6  965.09  4720.7  967.65  4790.9  968.83    4871  960.85  4921.2  958.54
  4958.4   952.8  4958.9   949.8  4989.9   949.8  4990.5   952.8  4991.3  953.85
  5081.5  964.25  5101.6  968.85  5118.5  969.34  5123.5  971.97  5176.4   975.3
    5203  981.22  5208.8  983.88    5214  983.33  5250.6  990.65  5357.4 1002.64
#Mann= 6 ,-1 , 0
    4143     .12       0  4412.9     .05       0  4682.3     .12       0
  4958.4     .07       0  4990.5     .12       0  5176.4     .05       0
Bank Sta=4958.4,4990.5
XS Rating Curve= 0 ,0
Exp/Cntr=0.3,0.1

Type RM Length L Ch R = 1 ,26365   ,567,567,567
BEGIN DESCRIPTION:
WALNUT CREEK 49.0
END DESCRIPTION:
XS GIS Cut Line= 3
      2884130.06     10160426.53      2884570.46      10159965.4
      2885064.75     10159388.56
#Sta/Elev= 30
  4245.2  1026.3  4265.6 1026.24    4287 1022.73  4357.8 1016.07  4492.1  999.44
  4583.9  990.86  4591.2  988.96  4619.5  986.11  4654.7   984.9  4668.8  981.75
  4724.2   976.6  4760.7  972.65  4824.5  966.13  4859.7  964.12  4887.8  960.57
  4903.2  960.17  4951.7  957.63  4965.7  953.19    5000  952.49  5000.6  949.49
  5031.9  949.49  5032.4  952.49  5037.1   954.1  5108.4  959.86  5143.6  964.53
  5235.8  969.33  5307.1  970.83  5402.7  976.94  5527.6  983.55  5642.5  990.12
#Mann= 8 ,-1 , 0
  4245.2     .12       0  4724.2     .05       0  4760.7     .12       0
  4903.2     .05       0    5000     .03       0  5032.4     .05       0
  5402.7     .05       0  5527.6     .12       0
Bank Sta=5000,5032.4
XS Rating Curve= 0 ,0
Exp/Cntr=0.3,0.1

Type RM Length L Ch R = 1 ,25798   ,474,474,474
BEGIN DESCRIPTION:
WALNUT CREEK 48.0
END DESCRIPTION:
XS GIS Cut Line= 3
      2885168.04     10160881.02      2885198.85     10159743.49
      2885199.03     10159331.74
#Sta/Elev= 30
  4012.5 1032.23  4040.4 1029.09  4107.8 1017.48  4112.8 1018.29  4120.5 1016.94
  4210.5 1012.09  4250.5 1004.86  4340.5  994.75  4450.6  986.85  4477.5  983.66
  4620.6  972.47  4750.7  967.69  4760.7  966.88  4810.7  956.66  4847.2  953.75
  4852.2  954.66  4860.7  954.25  4920.7  949.31  4940.8   946.3  5004.6  945.57
  5005.1  942.57  5036.5  942.57    5037  945.57  5040.8  947.71  5070.8  955.47
  5200.8  973.82  5340.8  982.24  5430.8  990.34  5507.5  995.57  5562.2  998.17
#Mann= 4 ,-1 , 0
  4012.5     .12       0  5004.6     .07       0    5037     .12       0
  5507.5     .05       0
Bank Sta=5004.6,5037
XS Rating Curve= 0 ,0
Exp/Cntr=0.3,0.1

Type RM Length L Ch R = 1 ,25324   ,496,496,496
BEGIN DESCRIPTION:
WALNUT CREEK 47.0
END DESCRIPTION:
XS GIS Cut Line= 3
      2885305.67     10160703.15        2885667.       10159891.
      2885705.68     10159453.11
#Sta/Elev= 30
  4111.1  1014.2  4125.5 1013.78    4172  1005.5  4241.7  998.26  4308.2  992.06
  4438.6  982.63  4467.4  979.38  4542.6  975.55  4565.8  972.76  4680.3  965.28
  4739.5  963.43  4866.6  956.17  4913.1  951.91  4930.9   948.6  4936.4  948.92
  4959.6   945.9  4965.1  946.35  4982.9  941.93    5028  942.84  5031.8  941.77
  5032.4  938.77  5063.8  938.77  5064.3  941.77  5068.2   946.9  5088.2  954.94
  5098.3  960.69  5118.3  965.36  5198.7  970.98  5329.2  975.66  5439.6  984.88
#Mann= 3 ,-1 , 0
  4111.1     .12       0  5031.8     .07       0  5064.3     .12       0
Bank Sta=5031.8,5064.3
XS Rating Curve= 0 ,0
Exp/Cntr=0.3,0.1

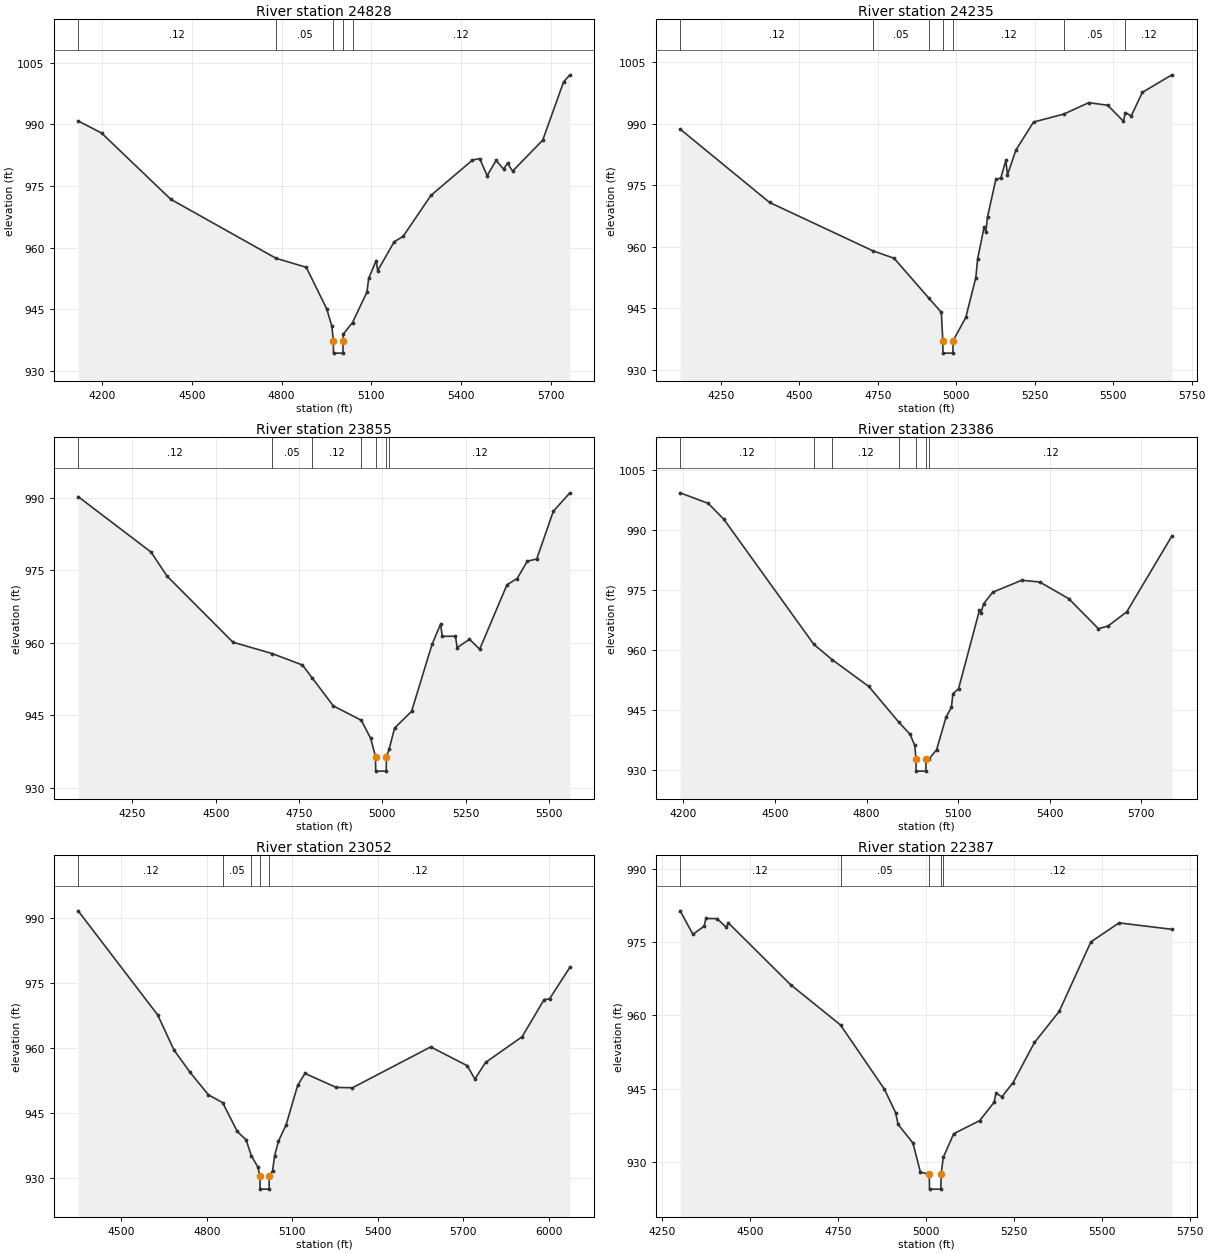
Type RM Length L Ch R = 1 ,24828   ,593,593,593
BEGIN DESCRIPTION:
WALNUT CREEK 46.0
END DESCRIPTION:
XS GIS Cut Line= 3
      2885787.74     10160731.25      2886102.76     10160080.56
      2886428.11     10159218.12
#Sta/Elev= 30
  4119.7  990.84  4198.1  987.89  4429.5  971.78  4781.2  957.43  4882.7  955.23
  4951.1  945.11  4968.2  940.95  4973.3  937.35  4973.8  934.35  5005.3  934.35
  5005.8  937.35  5006.2  938.96  5037.4   941.8  5085.7  949.21  5091.4  952.54
  5116.3  956.84  5121.6  954.43  5176.7  961.43  5206.9  962.78  5299.5  972.71
  5438.4  981.31  5462.6  981.68  5487.5  977.52  5517.6  981.22  5542.5  979.12
    5556  980.54  5572.7  978.62  5673.6  986.17  5743.2 1000.32  5764.4 1002.05
#Mann= 5 ,-1 , 0
  4119.7     .12       0  4781.2     .05       0  4973.3     .03       0
  5005.8     .05       0  5037.4     .12       0
Bank Sta=4973.3,5005.8
XS Rating Curve= 0 ,0
Exp/Cntr=0.3,0.1

Type RM Length L Ch R = 1 ,24235   ,380,380,380
BEGIN DESCRIPTION:
WALNUT CREEK 45.0
END DESCRIPTION:
XS GIS Cut Line= 3
      2886438.45     10160973.92       2886777.9     10159934.63
      2886944.52     10159491.86
#Sta/Elev= 30
  4120.7  988.67  4405.6  970.79    4734  959.03  4802.2  957.19  4912.6   947.5
  4952.6  944.02  4957.4  937.07  4957.9  934.07  4989.4  934.07    4990  937.07
  5030.6  942.78  5062.5  952.49  5068.3  957.05  5089.1  964.88  5094.4  963.67
  5099.9  967.33  5126.3  976.41    5142  976.75  5158.2  981.02  5163.4  977.52
    5190  983.55  5246.3  990.39  5342.9  992.34  5422.3  995.12  5482.8  994.48
  5532.5  990.59    5539   992.7  5557.4  991.87    5593  997.63  5687.1  1001.9
#Mann= 7 ,-1 , 0
  4120.7     .12       0    4734     .05       0  4912.6     .12       0
  4957.4     .07       0    4990     .12       0  5342.9     .05       0
    5539     .12       0
Bank Sta=4957.4,4990
XS Rating Curve= 0 ,0
Exp/Cntr=0.3,0.1

Type RM Length L Ch R = 1 ,23855   ,469,469,469
BEGIN DESCRIPTION:
WALNUT CREEK 44.0
END DESCRIPTION:
XS GIS Cut Line= 3
      2887207.89       10161165.      2887026.06     10160462.03
      2887180.68     10159728.15
#Sta/Elev= 30
    4087   990.3  4305.9  978.81  4353.9  973.84  4551.8  960.15  4669.4   957.8
  4760.3  955.43  4789.4  952.78  4852.9  946.97    4937  943.99  4965.3  940.23
  4979.6  936.46  4980.2  933.46  5011.8  933.46  5012.3  936.46  5020.4  937.96
  5036.8  942.37  5087.9  945.84  5149.2  959.69  5174.9   963.9    5180  961.38
  5219.6  961.38  5224.7  959.03  5261.7  960.76  5292.3   958.7  5374.1  972.03
  5404.7  973.34  5435.4  976.94  5463.5  977.37  5513.3  987.26  5563.1  991.08
#Mann= 7 ,-1 , 0
    4087     .12       0  4669.4     .05       0  4789.4     .12       0
    4937     .05       0  4979.6     .05       0  5012.3     .05       0
  5020.4     .12       0
Bank Sta=4979.6,5012.3
XS Rating Curve= 0 ,0
Exp/Cntr=0.3,0.1

Type RM Length L Ch R = 1 ,23386   ,334,334,334
BEGIN DESCRIPTION:
WALNUT CREEK 43.0
END DESCRIPTION:
XS GIS Cut Line= 3
      2887306.03     10161263.12      2887534.45      10160243.2
      2887424.81     10159688.11
#Sta/Elev= 30
    4189   999.3  4281.2  996.65  4332.5  992.65  4627.2  961.35    4687  957.54
  4807.1  950.83  4905.3   941.9  4942.3  938.84  4957.6  936.06  4961.7  932.64
  4962.3  929.64  4993.9  929.64  4994.4  932.64    5005  932.79  5029.1  934.98
  5060.1  943.15  5077.6  945.65  5082.7  949.02  5101.1  950.27  5169.4  969.86
  5174.6  969.21    5183  971.52  5212.8  974.41    5308  977.42  5366.8  976.98
  5461.8  972.82  5559.3  965.29    5591  965.97  5652.2  969.53    5800   988.5
#Mann= 7 ,-1 , 0
    4189     .12       0  4627.2     .05       0    4687     .12       0
  4905.3     .05       0  4961.7     .05       0  4994.4     .05       0
    5005     .12       0
Bank Sta=4961.7,4994.4
XS Rating Curve= 0 ,0
Exp/Cntr=0.3,0.1

Type RM Length L Ch R = 1 ,23052   ,665,665,665
BEGIN DESCRIPTION:
WALNUT CREEK 42.0
END DESCRIPTION:
XS GIS Cut Line= 3
      2887605.54     10161263.18      2887828.58     10160410.84
      2887569.83     10159606.79
#Sta/Elev= 30
  4348.5  991.77  4627.7  967.71  4684.7  959.62  4741.4  954.43  4805.9  949.24
  4855.9  947.42  4906.8  940.78  4937.8  938.86  4956.3  935.16  4979.1  932.57
  4986.5  930.45  4987.1  927.45  5018.7  927.45  5019.2  930.45  5030.8  931.69
  5038.1  935.17  5051.5  938.54  5078.6  942.36    5119  951.46  5144.5  954.19
  5254.4  950.95  5311.2  950.88  5585.7  960.32    5714  955.97  5740.8  952.89
  5778.1  956.72  5906.5  962.67  5983.5  971.24  6002.7  971.43  6074.2  978.72
#Mann= 5 ,-1 , 0
  4348.5     .12       0  4855.9     .05       0  4956.3     .12       0
  4986.5     .07       0  5019.2     .12       0
Bank Sta=4986.5,5019.2
XS Rating Curve= 0 ,0
Exp/Cntr=0.3,0.1

Type RM Length L Ch R = 1 ,22387   ,778,778,778
BEGIN DESCRIPTION:
WALNUT CREEK 41.0
END DESCRIPTION:
XS GIS Cut Line= 3
      2888178.76     10161511.09      2888481.74     10160596.58
      2888504.12     10160163.15
#Sta/Elev= 30
  4300.8  981.43  4337.1  976.61  4368.8  978.27  4374.1  979.86  4405.8  979.83
  4432.2  978.03  4437.5  978.98  4614.7  966.29  4756.5  958.03  4881.3  944.87
    4913  940.07  4920.2  937.64  4962.3  933.83  4983.4  927.91  5008.8  927.38
  5009.4  924.38  5041.6  924.38  5042.3  927.38  5048.5  930.89  5078.2  935.74
    5152  938.43    5193  942.19  5198.3  944.05  5215.2  943.31  5246.8  946.21
  5307.7  954.44  5377.8   960.8  5467.9  975.06    5548  978.96  5698.2  977.64
#Mann= 5 ,-1 , 0
  4300.8     .12       0  4756.5     .05       0  5008.8     .05       0
  5042.3     .05       0  5048.5     .12       0
Bank Sta=5008.8,5042.3
XS Rating Curve= 0 ,0
Exp/Cntr=0.3,0.1