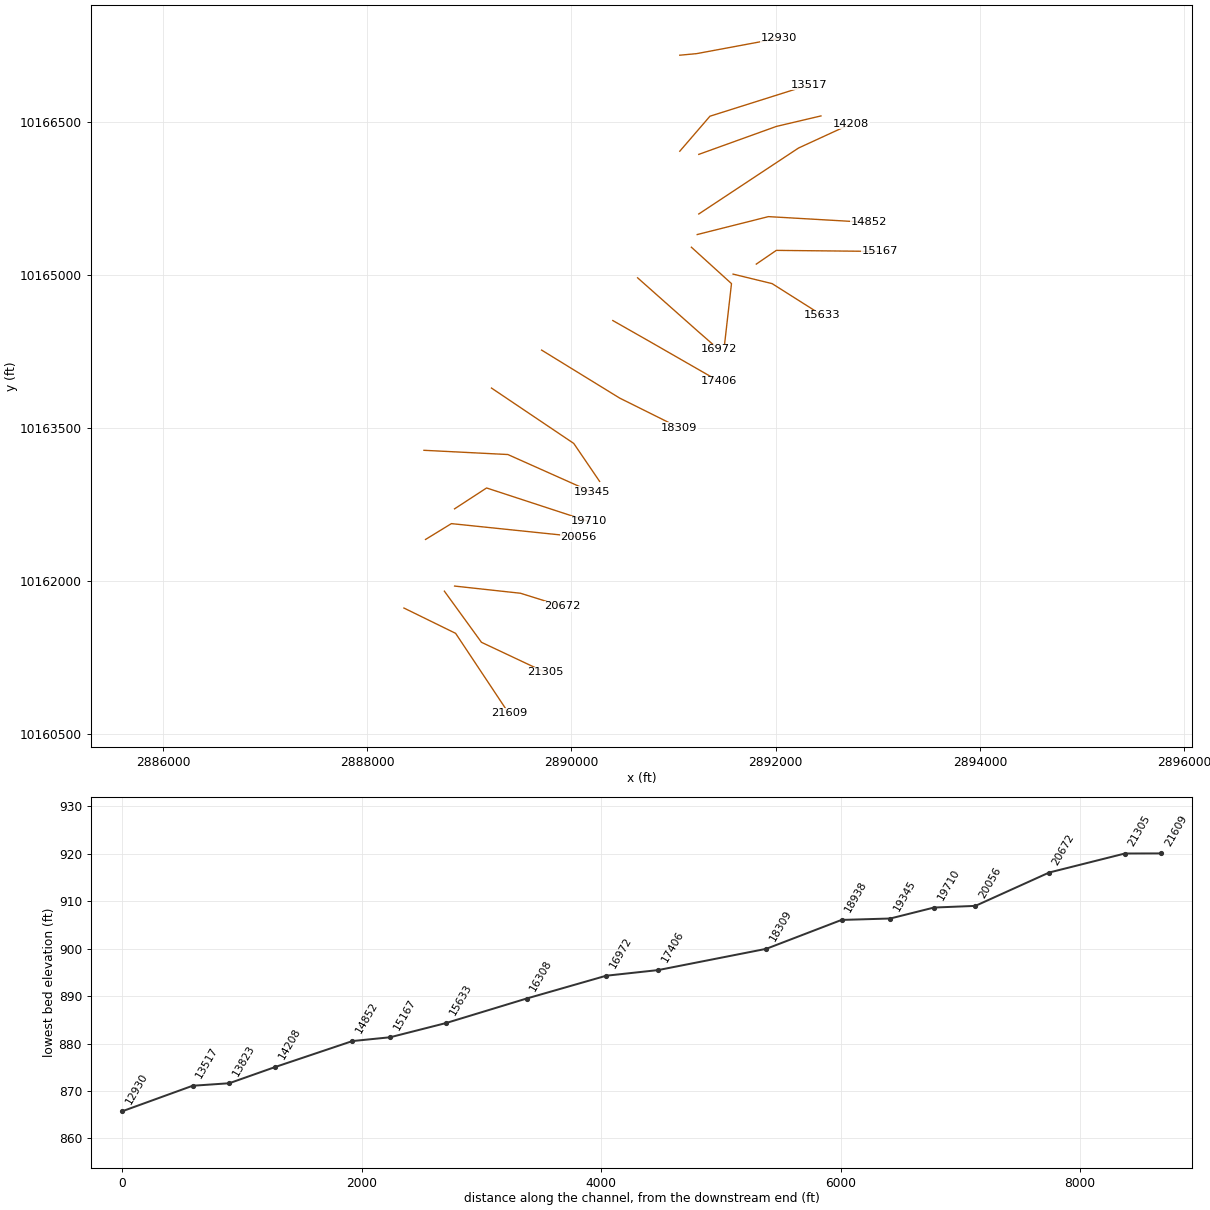
HEC-RAS study WALNUT CREEK.prj: WALNUT CREEK Base Level Engineering

--- WALNUT CREEK.g01 (geometry) --- (continued)

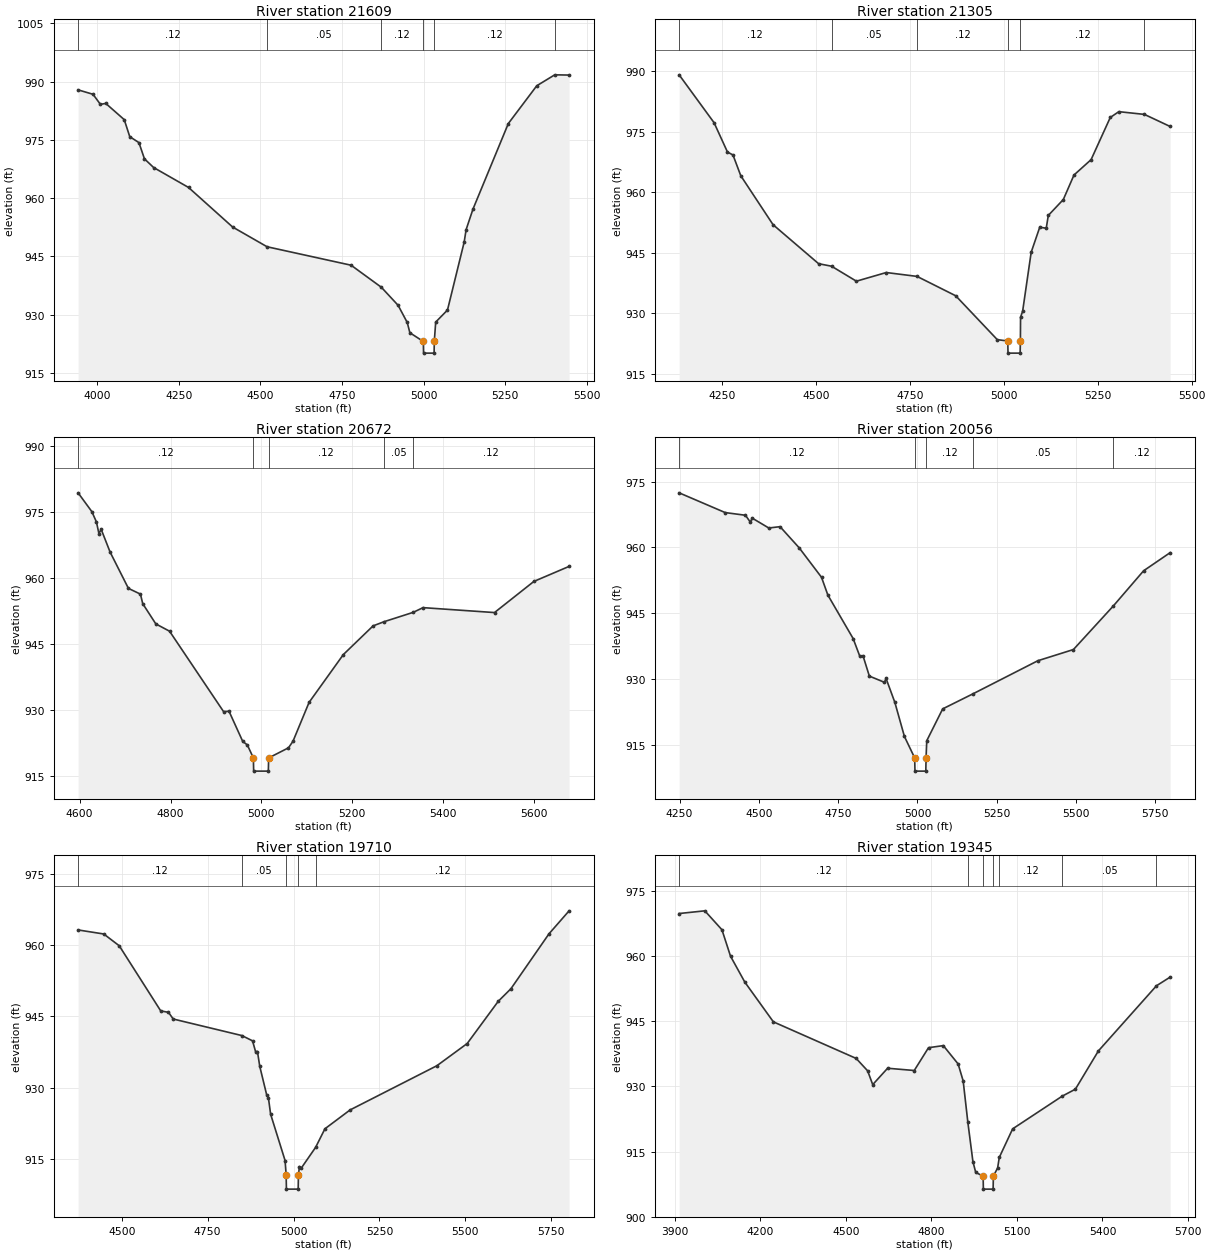
Type RM Length L Ch R = 1 ,21609   ,304,304,304
BEGIN DESCRIPTION:
WALNUT CREEK 40.0
END DESCRIPTION:
XS GIS Cut Line= 3
      2888359.55     10161738.25      2888865.61     10161490.38
      2889386.28      10160706.8
#Sta/Elev= 30
  3941.6  987.85  3987.4  986.71  4009.9  984.12  4026.4  984.36    4083  980.18
  4099.9   975.8    4128  974.27  4144.9  970.09    4173  967.86  4279.9  962.73
  4414.9  952.55  4520.6  947.46    4778  942.71  4870.6  937.04    4922  932.39
    4950  927.97  4958.1  925.32  4999.3  923.08    5000  920.08  5032.3  920.08
  5032.9  923.08  5037.2  928.07  5073.3  931.17  5124.4  948.65  5130.4  951.87
  5151.4  957.15  5259.7  979.18  5346.9  988.91  5401.9  991.72  5445.9  991.66
#Mann= 6 ,-1 , 0
  3941.6     .12       0  4520.6     .05       0  4870.6     .12       0
  4999.3     .07       0  5032.9     .12       0  5401.9     .05       0
Bank Sta=4999.3,5032.9
XS Rating Curve= 0 ,0
Exp/Cntr=0.3,0.1

Type RM Length L Ch R = 1 ,21305   ,633,633,633
BEGIN DESCRIPTION:
WALNUT CREEK 39.0
END DESCRIPTION:
XS GIS Cut Line= 3
      2888755.71     10161903.08      2889118.66     10161402.59
      2889742.11      10161108.9
#Sta/Elev= 30
  4135.3  989.12  4228.4  977.23    4264  969.96  4278.7  969.23  4299.5  964.07
  4385.4  951.93  4506.7  942.25  4541.1  941.63  4607.3  937.91  4686.9  940.06
  4768.8   939.1  4871.8  934.29  4982.4  923.41  5010.4  923.06    5011  920.06
  5043.3  920.06    5044  923.06  5044.4  928.98  5049.9  930.43  5072.7  945.09
  5095.5   951.3  5112.8  951.06  5118.3  954.23  5158.3  958.18  5186.7  964.26
  5232.2  968.07  5283.3  978.54  5306.1  979.98  5374.2   979.3  5442.7   976.3
#Mann= 6 ,-1 , 0
  4135.3     .12       0  4541.1     .05       0  4768.8     .12       0
  5010.4     .07       0    5044     .12       0  5374.2     .05       0
Bank Sta=5010.4,5044
XS Rating Curve= 0 ,0
Exp/Cntr=0.3,0.1

Type RM Length L Ch R = 1 ,20672   ,616,616,616
BEGIN DESCRIPTION:
WALNUT CREEK 38.0
END DESCRIPTION:
XS GIS Cut Line= 3
      2888855.65     10161953.12      2889500.81     10161882.86
      2889912.31     10161754.27
#Sta/Elev= 30
  4596.7  979.34  4626.9  975.07    4637  972.73  4642.5  970.07  4647.5  971.04
  4667.1  965.87  4707.4  957.61  4733.9   956.3  4738.9  954.13  4767.7  949.53
  4797.9  947.87  4916.8  929.57  4928.7  929.67  4958.9   922.8  4968.9  922.02
  4982.3  919.05  4982.9  916.05  5015.2  916.05  5015.9  919.05  5059.5  921.35
  5069.5  922.86  5104.8  931.68  5180.2  942.56  5245.6  949.08  5269.4  950.02
  5333.9  952.16  5355.5  953.23  5512.7  952.11  5599.3  959.19  5676.8  962.61
#Mann= 5 ,-1 , 0
  4596.7     .12       0  4982.3     .07       0  5015.9     .12       0
  5269.4     .05       0  5333.9     .12       0
Bank Sta=4982.3,5015.9
XS Rating Curve= 0 ,0
Exp/Cntr=0.3,0.1

Type RM Length L Ch R = 1 ,20056   ,346,346,346
BEGIN DESCRIPTION:
WALNUT CREEK 37.0
END DESCRIPTION:
XS GIS Cut Line= 3
      2888571.25     10162409.61       2888824.3     10162564.54
      2890068.91     10162435.43
#Sta/Elev= 30
  4248.6  972.42  4393.8  967.92  4457.7  967.31  4473.1  965.74    4479  966.66
  4531.2  964.41  4566.8  964.71  4627.1  959.89  4697.5  953.18  4717.6  949.11
  4797.2  939.22  4818.2  935.19  4828.2  935.32  4848.3  930.67    4896  929.25
    4901  930.13  4928.7  924.68  4958.9  916.91  4991.3  912.02  4992.1  909.02
  5026.3  909.02  5027.1  912.02  5029.3  915.95  5079.5   923.2  5175.8  926.66
  5379.5  934.17  5491.7  936.72  5617.5  946.65  5712.9  954.66  5796.6  958.79
#Mann= 5 ,-1 , 0
  4248.6     .12       0  4991.3     .07       0  5027.1     .12       0
  5175.8     .05       0  5617.5     .12       0
Bank Sta=4991.3,5027.1
XS Rating Curve= 0 ,0
Exp/Cntr=0.3,0.1

Type RM Length L Ch R = 1 ,19710   ,365,365,365
BEGIN DESCRIPTION:
WALNUT CREEK 36.0
END DESCRIPTION:
XS GIS Cut Line= 3
      2888855.32     10162709.16      2889168.93     10162913.63
       2890171.4     10162585.44
#Sta/Elev= 30
    4373  963.17  4447.7  962.32  4492.8  959.84  4613.6  946.14  4636.1  945.85
  4649.9  944.44  4849.8  940.96  4880.8  939.85  4889.8  937.53  4895.1  937.59
  4901.8  934.48  4921.7  928.56    4927  927.86  4933.4  924.42  4975.5  914.68
  4978.6  911.67  4979.4  908.67  5013.6  908.67  5014.4  911.67  5017.3  913.42
  5022.5  913.08  5064.5  917.47  5091.5  921.36  5164.9  925.33  5417.4  934.62
  5505.6  939.29  5595.9  948.16    5633  950.82  5743.6  962.35  5802.2  967.19
#Mann= 5 ,-1 , 0
    4373     .12       0  4849.8     .05       0  4978.6     .05       0
  5014.4     .05       0  5064.5     .12       0
Bank Sta=4978.6,5014.4
XS Rating Curve= 0 ,0
Exp/Cntr=0.3,0.1

Type RM Length L Ch R = 1 ,19345   ,407,407,407
BEGIN DESCRIPTION:
WALNUT CREEK 35.0
END DESCRIPTION:
XS GIS Cut Line= 3
      2888555.73     10163282.36      2889376.87     10163241.05
      2890197.95      10162874.4
#Sta/Elev= 30
  3915.8  969.81  4005.9  970.43  4065.9  966.07    4096  959.98    4146  954.03
  4246.2  944.87  4536.5  936.45  4576.6   933.6  4594.5  930.42  4646.7  934.19
  4740.1  933.67  4790.1  938.92    4842   939.4  4893.9  935.18  4911.6  931.27
    4928  921.75  4945.8  912.69  4955.7  910.19  4981.6  909.36  4982.4  906.36
  5016.6  906.36  5017.5  909.36  5032.4  911.23  5038.2  913.66  5085.1  920.24
  5258.7  927.76    5305  929.37  5385.6  938.17  5589.3  953.18  5637.2  955.17
#Mann= 7 ,-1 , 0
  3915.8     .12       0    4928     .05       0  4981.6     .05       0
  5017.5     .05       0  5038.2     .12       0  5258.7     .05       0
  5589.3     .12       0
Bank Sta=4981.6,5017.5
XS Rating Curve= 0 ,0
Exp/Cntr=0.3,0.1

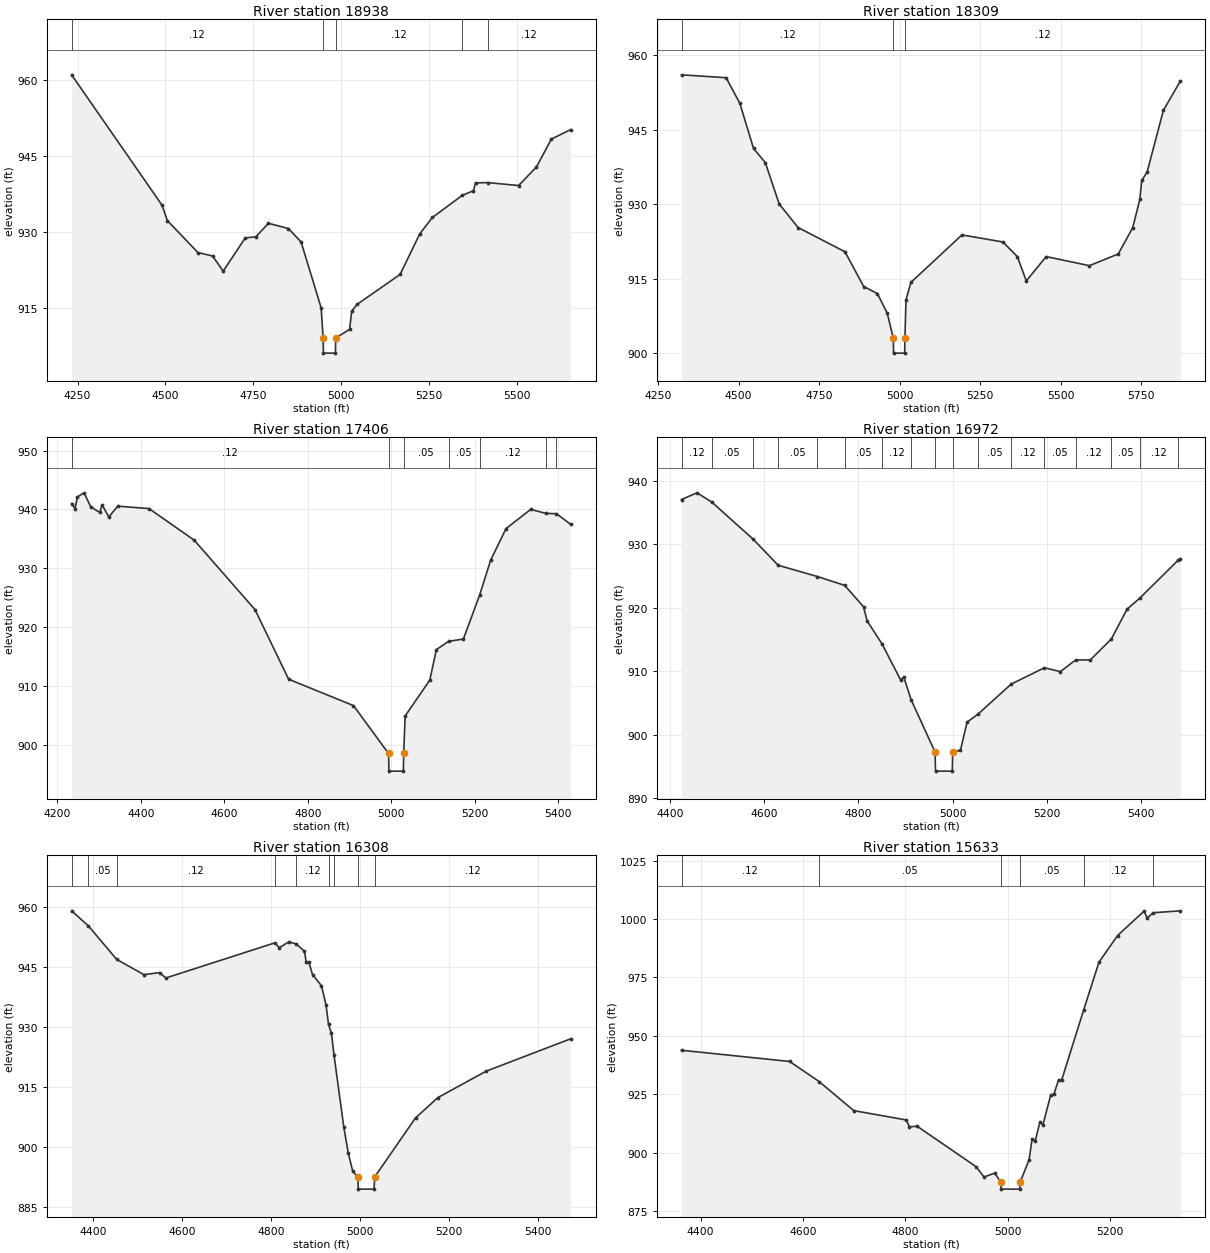
Type RM Length L Ch R = 1 ,18938   ,629,629,629
BEGIN DESCRIPTION:
WALNUT CREEK 34.0
END DESCRIPTION:
XS GIS Cut Line= 3
      2889216.76     10163891.75      2890022.39      10163349.5
      2890275.28     10162977.91
#Sta/Elev= 30
  4232.9  961.02  4490.5  935.26  4505.4  932.24  4592.4  925.93  4634.4  925.24
  4664.4  922.25  4727.4  928.82  4757.4  929.03  4793.4   931.7  4850.4  930.66
  4886.3  928.01  4943.3  915.02    4949  909.06  4949.8  906.06    4984  906.06
  4984.9  909.06  5024.3  910.74  5030.3  914.32  5045.3  915.67  5168.2   921.6
  5224.3  929.63  5260.2  932.86  5345.7  937.24  5376.9  938.13  5382.9  939.68
  5417.1  939.74  5505.6  939.16  5556.5  942.83  5598.8  948.33  5653.5  950.19
#Mann= 5 ,-1 , 0
  4232.9     .12       0    4949     .07       0  4984.9     .12       0
  5345.7     .05       0  5417.1     .12       0
Bank Sta=4949,4984.9
XS Rating Curve= 0 ,0
Exp/Cntr=0.3,0.1

Type RM Length L Ch R = 1 ,18309   ,903,903,903
BEGIN DESCRIPTION:
WALNUT CREEK 33.0
END DESCRIPTION:
XS GIS Cut Line= 3
       2889707.4     10164263.55      2890471.68     10163793.62
      2891055.71      10163503.1
#Sta/Elev= 30
  4322.5  956.07    4461  955.49  4503.6  950.33  4546.1  941.24  4582.8  938.37
  4625.7  930.05  4684.4  925.29  4830.2   920.4  4888.2   913.4  4930.9  911.97
  4961.6  907.98  4980.2  902.97    4981  899.97  5015.5  899.97  5016.3  902.97
  5019.6  910.72    5035  914.24  5193.5   923.8  5320.5  922.38  5365.3  919.44
  5393.3  914.52  5454.9  919.43  5589.2   917.6  5678.8  919.96  5723.6  925.24
    5746     931  5751.6  934.77  5768.4  936.46  5818.8  948.88    5872  954.86
#Mann= 3 ,-1 , 0
  4322.5     .12       0  4980.2     .07       0  5016.3     .12       0
Bank Sta=4980.2,5016.3
XS Rating Curve= 0 ,0
Exp/Cntr=0.3,0.1

Type RM Length L Ch R = 1 ,17406   ,434,434,434
BEGIN DESCRIPTION:
WALNUT CREEK 32.0
END DESCRIPTION:
XS GIS Cut Line= 3
      2890404.53     10164552.76      2890755.68     10164353.11
      2891441.59     10163959.42
#Sta/Elev= 30
  4234.3  940.98  4242.5  940.15  4248.3  942.14  4264.2  942.82    4280  940.45
  4301.6  939.48  4307.4  940.76  4323.3  938.73  4344.9  940.55  4419.7  940.14
    4528  934.76  4673.5  922.95    4754  911.12  4909.3  906.63  4993.3  898.49
  4994.2  895.49  5028.7  895.49  5029.5  898.49    5033  904.87    5092  910.96
  5107.8  916.16    5137  917.56  5172.5  917.96  5211.5  925.46  5237.8  931.38
  5274.6  936.74  5333.6     940  5370.4  939.32  5395.3  939.27  5429.1  937.47
#Mann= 7 ,-1 , 0
  4234.3     .12       0  4993.3     .07       0  5029.5     .05       0
    5137     .05       0  5211.5     .12       0  5370.4     .05       0
  5395.3     .12       0
Bank Sta=4993.3,5029.5
XS Rating Curve= 0 ,0
Exp/Cntr=0.3,0.1

Type RM Length L Ch R = 1 ,16972   ,664,664,664
BEGIN DESCRIPTION:
WALNUT CREEK 31.0
END DESCRIPTION:
XS GIS Cut Line= 3
      2890647.28     10164971.04      2891241.15     10164444.31
      2891441.65     10164269.51
#Sta/Elev= 30
  4424.3  937.04  4457.2  938.09  4488.2  936.66  4575.8  930.84  4629.6  926.69
  4712.9  924.92  4770.9  923.53    4811  920.15  4818.5  917.94  4850.1  914.33
  4889.6  908.66  4896.3   909.1  4912.2   905.5  4962.8   897.3  4963.8   894.3
  4999.4   894.3  5000.3   897.3  5016.7  897.57  5030.9  902.01  5053.6  903.24
  5124.4  907.99  5194.9  910.56  5229.1  909.96  5261.2  911.78  5292.7  911.81
  5337.3  915.09  5370.6  919.78  5397.3  921.49  5479.9  927.54  5484.1  927.67
#Mann= 17 ,-1 , 0
  4424.3     .12       0  4488.2     .05       0  4575.8     .12       0
  4629.6     .05       0  4712.9     .12       0  4770.9     .05       0
  4850.1     .12       0  4912.2     .05       0  4962.8     .07       0
  5000.3     .05       0  5053.6     .05       0  5124.4     .12       0
  5194.9     .05       0  5261.2     .12       0  5337.3     .05       0
  5397.3     .12       0  5479.9     .05       0
Bank Sta=4962.8,5000.3
XS Rating Curve= 0 ,0
Exp/Cntr=0.3,0.1

Type RM Length L Ch R = 1 ,16308   ,675,675,675
BEGIN DESCRIPTION:
WALNUT CREEK 30.0
END DESCRIPTION:
XS GIS Cut Line= 3
      2891173.98     10165270.61      2891566.49     10164914.25
       2891499.5     10164326.81
#Sta/Elev= 30
  4351.8  958.94  4389.7  955.16  4453.2  946.81  4514.3  943.02  4549.4  943.53
  4563.6  942.18  4808.8  950.96  4818.4  949.74    4840  951.19  4856.6  950.68
  4875.2  948.84  4879.1  946.12    4885  946.12  4893.2  943.05  4913.3  940.26
  4923.4  935.56  4929.3  930.59  4935.8  928.35  4941.5  922.96  4963.6  904.95
  4973.7  898.45  4983.7  893.95  4995.2   892.5  4996.1   889.5  5031.7   889.5
  5032.7   892.5  5124.7  907.27    5175  912.34  5283.5  918.93  5473.2     927
#Mann= 9 ,-1 , 0
  4351.8     .12       0  4389.7     .05       0  4453.2     .12       0
  4808.8     .05       0  4856.6     .12       0  4929.3     .05       0
  4941.5     .12       0  4995.2     .07       0  5032.7     .12       0
Bank Sta=4995.2,5032.7
XS Rating Curve= 0 ,0
Exp/Cntr=0.3,0.1

Type RM Length L Ch R = 1 ,15633   ,466,466,466
BEGIN DESCRIPTION:
WALNUT CREEK 29.0
END DESCRIPTION:
XS GIS Cut Line= 3
      2891581.98     10165007.21      2891964.14     10164914.25
      2892455.65     10164603.13
#Sta/Elev= 30
  4362.7  943.82    4574  939.02  4631.7   930.4  4699.2  917.97  4802.1  913.94
    4808  911.03  4823.2  911.25  4938.5  893.92  4953.8  889.51    4975   891.2
  4986.4  887.32  4987.4  884.32  5023.5  884.32  5024.5  887.32  5041.9  896.92
  5047.9  905.93  5053.8  904.88  5063.1  913.15    5069  911.92  5084.3  924.79
  5090.2  924.89  5099.6   931.2  5105.5  931.01  5148.5  961.06  5178.4  981.54
  5214.8  992.98  5266.6 1003.45  5272.5 1000.52    5285 1002.75  5337.7 1003.56
#Mann= 6 ,-1 , 0
  4362.7     .12       0  4631.7     .05       0  4986.4     .05       0
  5024.5     .05       0  5148.5     .12       0    5285     .05       0
Bank Sta=4986.4,5024.5
XS Rating Curve= 0 ,0
Exp/Cntr=0.3,0.1

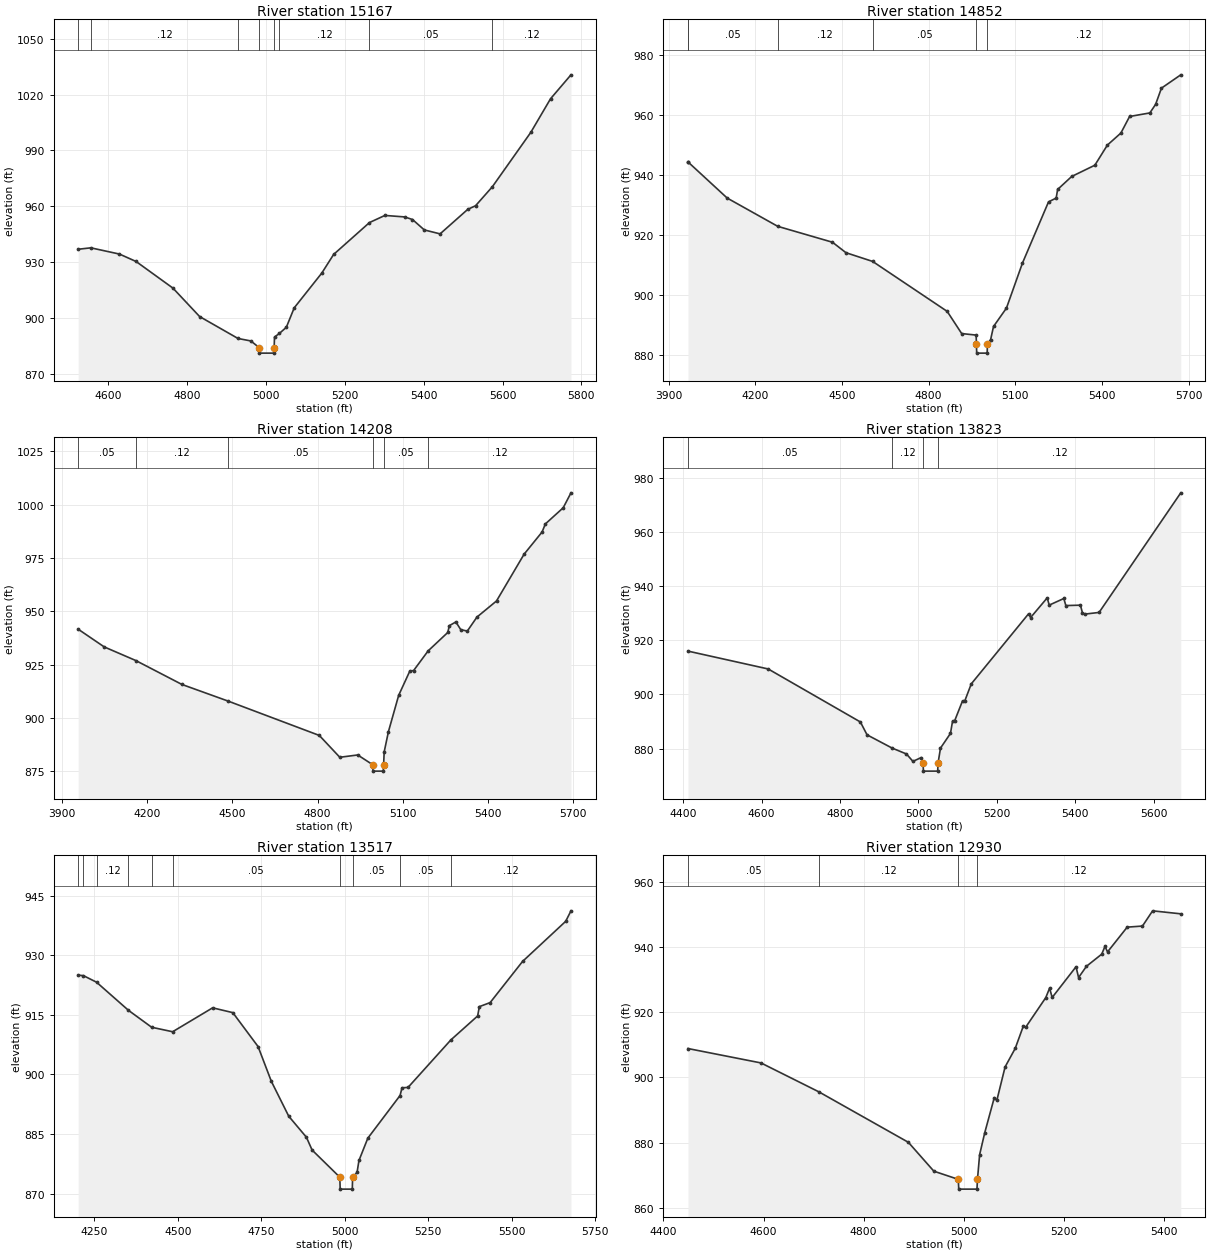
Type RM Length L Ch R = 1 ,15167   ,315,315,315
BEGIN DESCRIPTION:
WALNUT CREEK 28.0
END DESCRIPTION:
XS GIS Cut Line= 3
      2891809.21     10165105.33      2892005.45      10165239.6
      2893017.63     10165229.27
#Sta/Elev= 30
  4523.6  937.02  4555.7  937.79  4628.4  934.44  4670.5  930.46    4764  916.18
  4831.6  900.95  4929.1  889.18  4961.6  887.86  4982.5  884.33  4983.5  881.33
  5019.7  881.33  5020.7  884.33  5021.6  889.95  5034.2  891.93  5051.6  895.19
  5071.6  905.62  5141.6  924.27  5171.6  934.26  5262.5  951.34  5301.6  955.16
  5351.6  954.36  5371.6  952.97  5401.6  947.38  5441.6  945.27  5511.6  958.39
  5531.6  960.36  5574.2  970.55  5671.7   999.7  5721.7  1017.7  5773.6 1030.55
#Mann= 8 ,-1 , 0
  4523.6     .05       0  4555.7     .12       0  4929.1     .05       0
  4982.5     .05       0  5020.7     .05       0  5034.2     .12       0
  5262.5     .05       0  5574.2     .12       0
Bank Sta=4982.5,5020.7
XS Rating Curve= 0 ,0
Exp/Cntr=0.3,0.1

Type RM Length L Ch R = 1 ,14852   ,644,644,644
BEGIN DESCRIPTION:
WALNUT CREEK 27.0
END DESCRIPTION:
XS GIS Cut Line= 3
      2891230.81     10165394.52      2891927.99      10165570.1
      2892912.51      10165513.4
#Sta/Elev= 30
  3967.3  944.16  3968.3  944.16    4103   932.2  4277.9  922.78  4467.3  917.48
    4514  913.99  4606.2  911.09  4864.2  894.44  4914.3  887.05  4964.4  886.54
  4965.3  883.53  4966.3  880.53  5002.5  880.53  5003.5  883.53  5014.5  885.06
  5024.5  889.41  5069.2  895.53  5124.7  910.56  5214.8  930.93  5241.3  932.21
  5246.3  935.07    5295   939.4  5375.1  943.15  5418.4  949.85  5465.2  953.87
  5495.3  959.39  5565.4  960.57  5585.4  963.44  5605.5  968.83  5672.4  973.27
#Mann= 6 ,-1 , 0
  3967.3     .12       0  3968.3     .05       0  4277.9     .12       0
  4606.2     .05       0  4965.3     .07       0  5003.5     .12       0
Bank Sta=4965.3,5003.5
XS Rating Curve= 0 ,0
Exp/Cntr=0.3,0.1

Type RM Length L Ch R = 1 ,14208   ,385,385,385
BEGIN DESCRIPTION:
WALNUT CREEK 26.0
END DESCRIPTION:
XS GIS Cut Line= 3
      2891246.34     10165595.94      2892222.35     10166241.45
      2892737.77     10166478.55
#Sta/Elev= 30
  3956.1  941.64    4048  933.33  4159.2  926.95  4321.8  915.73  4485.4  907.89
  4806.3  891.81  4878.5  881.57  4941.7  882.65  4994.7  878.07  4995.7  875.07
    5032  875.07    5033  878.07    5035  884.08    5050   893.6  5086.1  910.63
  5125.3  921.98  5138.8  922.26    5190  931.48  5259.2  940.11  5264.7   943.3
  5287.7  945.05  5305.1  941.41  5328.1  940.77  5362.1  947.33    5431  954.88
  5528.4  976.85  5591.8  987.25  5603.2  991.01  5666.2   998.6  5693.6 1005.61
#Mann= 6 ,-1 , 0
  3956.1     .05       0  4159.2     .12       0  4485.4     .05       0
  4994.7     .05       0    5033     .05       0    5190     .12       0
Bank Sta=4994.7,5033
XS Rating Curve= 0 ,0
Exp/Cntr=0.3,0.1

Type RM Length L Ch R = 1 ,13823   ,306,306,306
BEGIN DESCRIPTION:
WALNUT CREEK 25.0
END DESCRIPTION:
XS GIS Cut Line= 3
      2891246.34     10166179.49      2892005.68     10166453.11
      2892442.58     10166556.04
#Sta/Elev= 30
  4412.6  916.05  4617.1  909.44    4852  889.83    4869  885.07  4932.9  880.17
  4969.5  877.98  4985.9  875.25  5007.2  876.67  5011.7  874.64  5012.7  871.64
    5049  871.64    5050  874.64  5056.2  880.16  5081.6  885.59  5086.9   890.1
  5092.2  890.24  5112.3  897.61  5117.6  897.43  5134.7  903.94  5280.7  929.86
  5285.8  928.46  5328.2  935.75  5333.3  933.07  5370.5  935.52  5375.7   932.9
  5412.9  933.05    5418  930.19  5425.2  929.76  5460.4  930.36  5668.6  974.62
#Mann= 4 ,-1 , 0
  4412.6     .05       0  4932.9     .12       0  5011.7     .07       0
    5050     .12       0
Bank Sta=5011.7,5050
XS Rating Curve= 0 ,0
Exp/Cntr=0.3,0.1

Type RM Length L Ch R = 1 ,13517   ,587,587,587
BEGIN DESCRIPTION:
WALNUT CREEK 24.0
END DESCRIPTION:
XS GIS Cut Line= 3
      2891060.39     10166210.45      2891355.68     10166553.11
      2892330.75     10166861.14
#Sta/Elev= 30
    4202  924.97  4217.8  924.85    4257   923.2  4352.5  916.12  4421.9  911.86
  4484.7  910.73  4604.4  916.75  4664.8  915.54  4740.4     907  4780.2  898.23
  4832.2  889.46  4885.1  884.17  4902.1  880.95  4985.1  874.11  4986.1  871.11
  5022.4  871.11  5023.4  874.11  5036.6   875.3  5042.4  878.33  5068.9  883.94
  5165.4  894.68  5171.2  896.62  5189.2  896.71  5317.4  908.67  5397.5   914.7
  5402.7  917.05    5435  918.07    5532  928.43  5661.1  938.53  5676.9  941.17
#Mann= 10 ,-1 , 0
    4202     .12       0  4217.8     .05       0    4257     .12       0
  4352.5     .05       0  4421.9     .12       0  4484.7     .05       0
  4985.1     .07       0  5023.4     .05       0  5165.4     .05       0
  5317.4     .12       0
Bank Sta=4985.1,5023.4
XS Rating Curve= 0 ,0
Exp/Cntr=0.3,0.1

Type RM Length L Ch R = 1 ,12930   ,415,415,415
BEGIN DESCRIPTION:
WALNUT CREEK 23.0
END DESCRIPTION:
XS GIS Cut Line= 3
      2891060.41     10167150.35      2891225.65     10167165.84
      2892030.99     10167315.55
#Sta/Elev= 30
    4449  908.84  4594.9  904.43  4710.7  895.56  4889.6  880.09  4940.5  871.24
  4989.3  868.74  4990.3  865.74  5026.7  865.74  5027.7  868.74    5032   876.3
  5042.2  883.01  5061.3  893.79  5066.4  892.95  5082.9   903.2  5103.2   908.9
  5119.1  915.61  5124.2   915.4  5164.2  924.44  5171.9  927.36    5177  924.49
  5224.7  933.91  5229.8  930.61  5245.6  934.06  5276.1  937.78  5282.6  940.17
  5287.7  938.46    5327  946.06  5357.5  946.39  5377.8  951.06  5434.1  950.14
#Mann= 4 ,-1 , 0
    4449     .05       0  4710.7     .12       0  4989.3     .07       0
  5027.7     .12       0
Bank Sta=4989.3,5027.7
XS Rating Curve= 0 ,0
Exp/Cntr=0.3,0.1