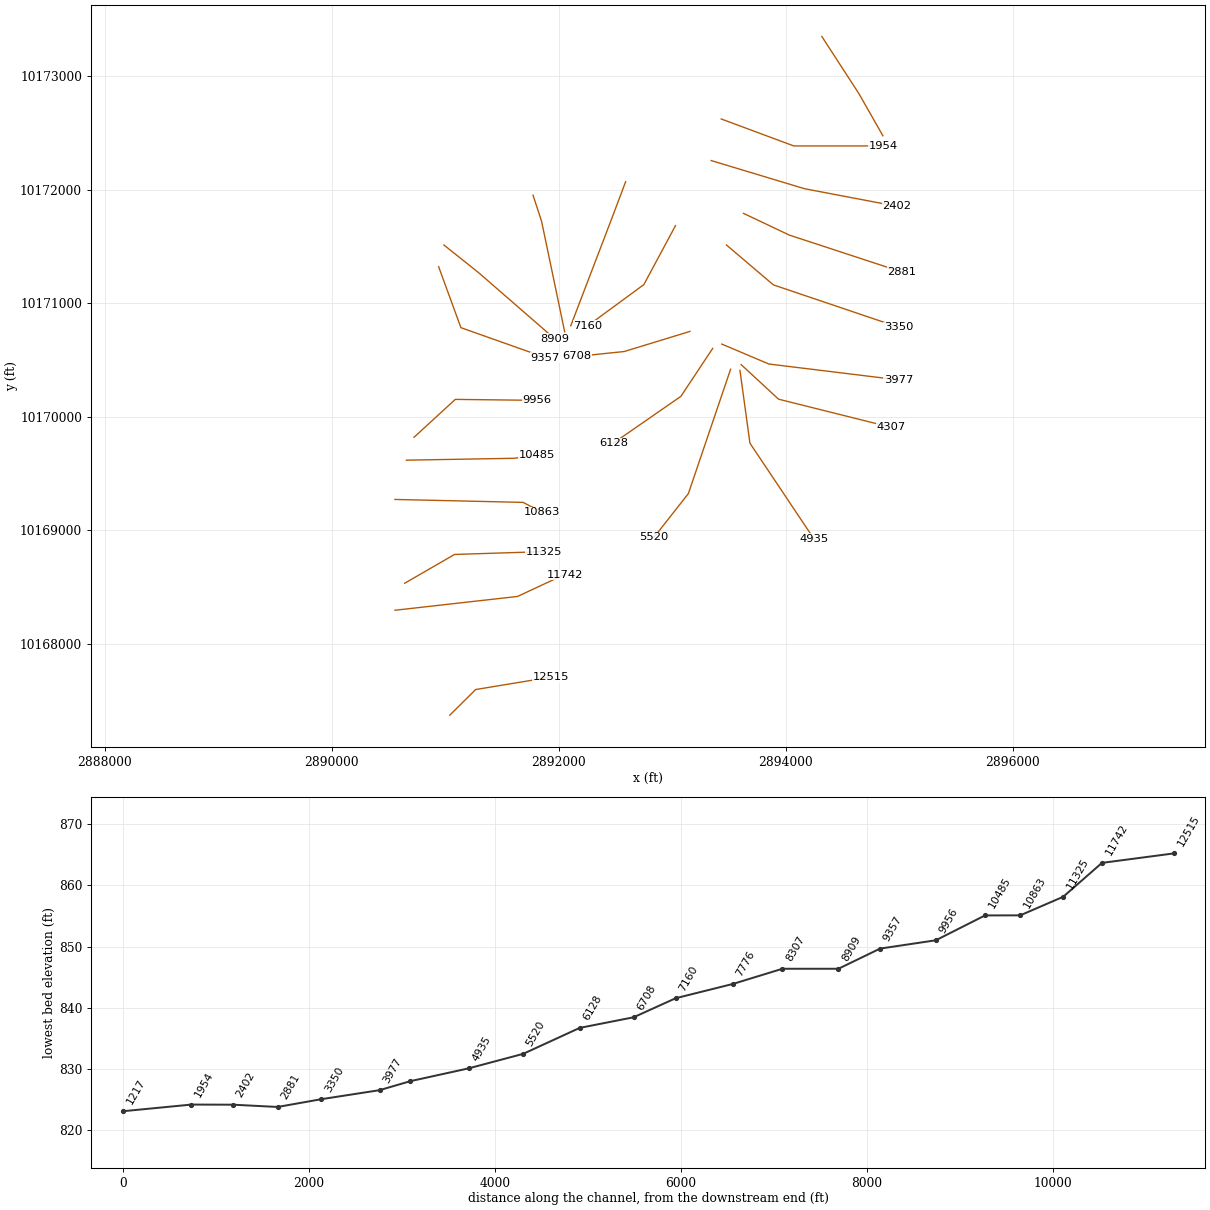
HEC-RAS study WALNUT CREEK.prj: WALNUT CREEK Base Level Engineering

--- WALNUT CREEK.g01 (geometry) --- (continued)

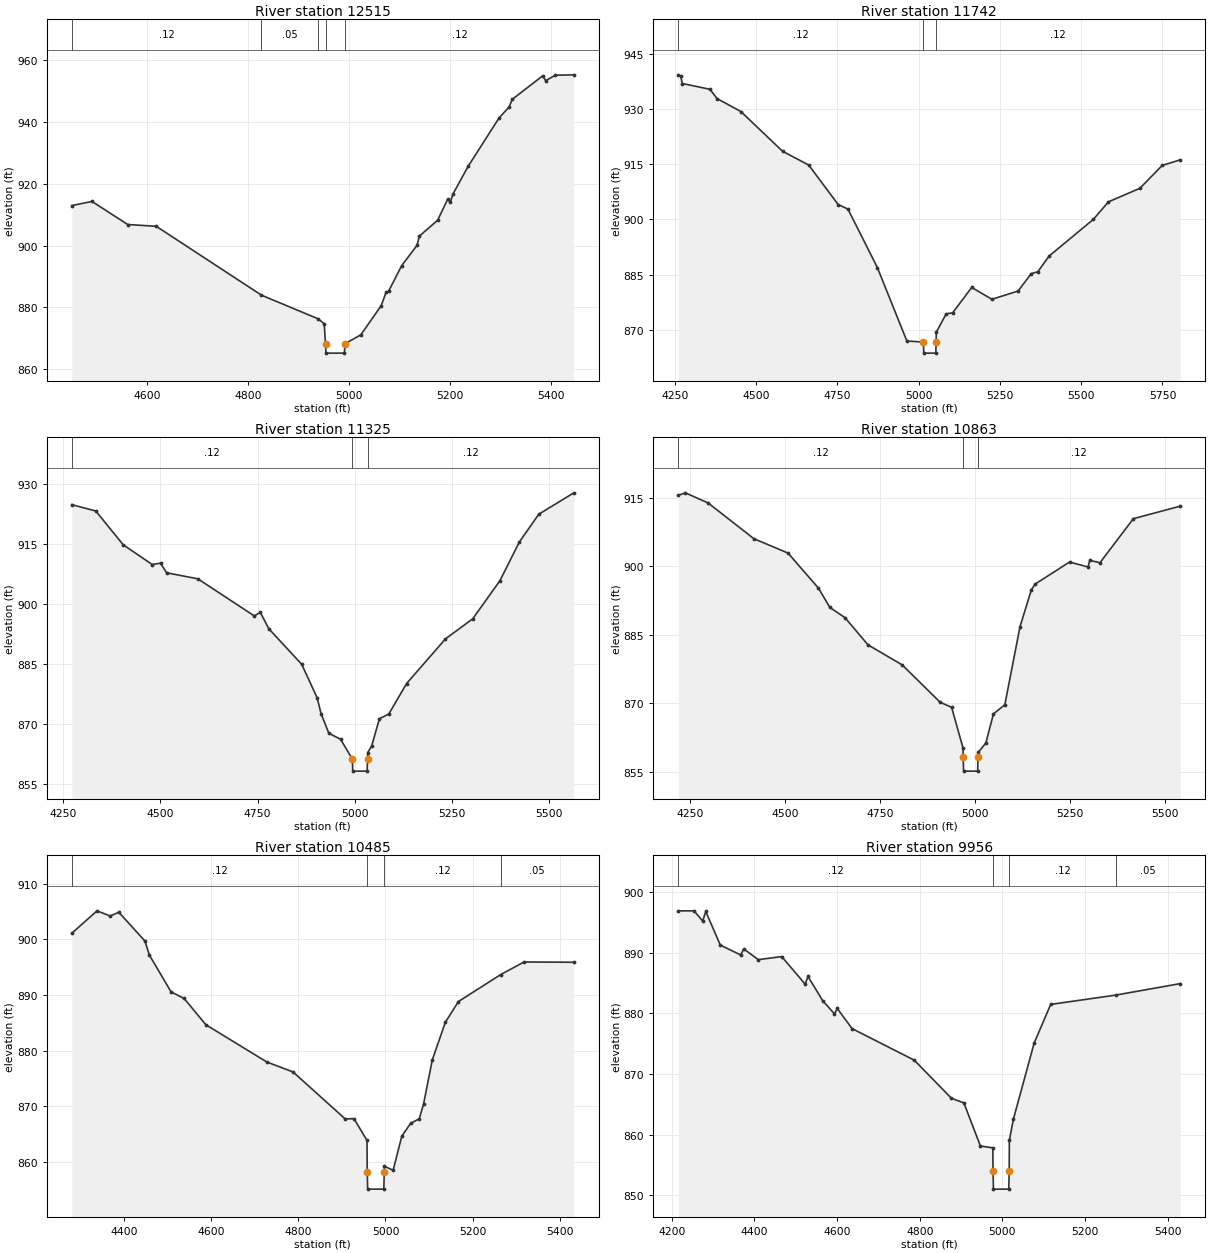
Type RM Length L Ch R = 1 ,12515   ,773,773,773
BEGIN DESCRIPTION:
WALNUT CREEK 22.0
END DESCRIPTION:
XS GIS Cut Line= 3
      2891039.74     10167372.41      2891267.94     10167598.47
      2891931.87     10167707.88
#Sta/Elev= 30
  4451.6  912.93  4491.6  914.28  4562.4  906.82  4618.9  906.24  4827.2  883.98
  4939.4  876.34  4951.5  874.74    4954  868.25    4955  865.25  4991.5  865.25
  4992.5  868.25  5023.9  871.18  5064.4  880.61  5073.8  884.88  5078.9  885.28
    5105  893.57    5135  900.04    5140   903.1  5175.9  908.18  5196.1  915.05
  5201.2     914  5206.3  916.66  5236.7   925.7  5297.5  941.23  5317.8  944.86
  5323.5  947.25  5384.7  954.96  5389.7  953.31    5409  955.07  5445.7   955.2
#Mann= 5 ,-1 , 0
  4451.6     .12       0  4827.2     .05       0  4939.4     .12       0
    4954     .07       0  4992.5     .12       0
Bank Sta=4954,4992.5
XS Rating Curve= 0 ,0
Exp/Cntr=0.3,0.1

Type RM Length L Ch R = 1 ,11742   ,417,417,417
BEGIN DESCRIPTION:
WALNUT CREEK 21.0
END DESCRIPTION:
XS GIS Cut Line= 3
      2890557.08     10168296.81      2891636.64     10168418.35
      2892051.27     10168611.52
#Sta/Elev= 30
    4261   939.3  4268.6  938.86  4273.7  936.94  4358.6  935.37  4380.4  932.85
  4453.6  929.33  4581.6  918.55  4662.1   914.8  4752.7  904.07  4782.9  902.82
  4873.4  886.92    4964     867    5015   866.7    5016   863.7    5053   863.7
    5054   866.7  5054.6   869.4  5084.8  874.36  5104.9  874.66  5163.4  881.54
  5225.7  878.32  5306.2  880.58  5346.3  885.29  5366.7  885.81  5401.5  890.08
  5537.8  900.06  5583.6  904.79  5680.6  908.48  5749.2  914.69  5804.8  916.21
#Mann= 3 ,-1 , 0
    4261     .12       0    5015     .07       0    5054     .12       0
Bank Sta=5015,5054
XS Rating Curve= 0 ,0
Exp/Cntr=0.3,0.1

Type RM Length L Ch R = 1 ,11325   ,462,462,462
BEGIN DESCRIPTION:
WALNUT CREEK 20.0
END DESCRIPTION:
XS GIS Cut Line= 3
      2890642.06     10168534.33      2891081.89     10168788.36
      2891865.98     10168813.22
#Sta/Elev= 30
  4271.7  924.74  4333.5  923.15    4404  914.72  4478.6  909.78  4500.1   910.1
  4515.9  907.71  4596.3   906.2  4741.4  896.94  4757.1  897.81  4778.7  893.75
  4863.5  884.85  4903.5  876.43  4913.5  872.47  4933.5   867.6  4963.5  866.13
    4994  861.15    4995  858.15    5032  858.15    5033  861.15  5033.5   862.8
  5043.5  864.37  5063.6  871.23  5087.9  872.45  5133.6  880.04  5233.6  891.19
  5303.7   896.2  5373.7  905.71  5423.7  915.38  5473.8  922.34  5564.1  927.69
#Mann= 3 ,-1 , 0
  4271.7     .12       0    4994     .07       0    5033     .12       0
Bank Sta=4994,5033
XS Rating Curve= 0 ,0
Exp/Cntr=0.3,0.1

Type RM Length L Ch R = 1 ,10863   ,378,378,378
BEGIN DESCRIPTION:
WALNUT CREEK 19.0
END DESCRIPTION:
XS GIS Cut Line= 3
      2890557.08     10169272.84      2891685.27     10169247.02
       2891855.7     10169159.22
#Sta/Elev= 30
  4219.8  915.59  4238.4  916.15  4298.4  913.93  4418.5   906.1  4508.5  902.93
  4588.5  895.25  4618.5  891.01  4658.5  888.76  4718.5  882.82  4808.6  878.41
  4908.6  870.21  4938.6  869.11  4968.6  860.19  4969.1  858.11  4970.1  855.11
  5007.1  855.11  5008.1  858.11  5008.6  859.21  5028.6  861.26  5048.6  867.65
  5078.6  869.68  5118.6  886.83  5148.6  894.93  5158.6  896.15  5248.7  900.97
  5297.1  899.89  5302.1  901.34  5328.7  900.82  5416.6  910.48    5540  913.23
#Mann= 3 ,-1 , 0
  4219.8     .12       0  4969.1     .07       0  5008.1     .12       0
Bank Sta=4969.1,5008.1
XS Rating Curve= 0 ,0
Exp/Cntr=0.3,0.1

Type RM Length L Ch R = 1 ,10485   ,529,529,529
BEGIN DESCRIPTION:
WALNUT CREEK 18.0
END DESCRIPTION:
XS GIS Cut Line= 3
      2890657.58     10169618.84       2891606.3     10169635.43
      2891809.23     10169660.16
#Sta/Elev= 30
  4279.4  901.07  4337.5  905.11  4367.5  904.18  4387.5  904.85  4447.5  899.68
  4457.5  897.18  4507.5  890.55  4537.5  889.36  4587.6  884.63  4727.6  877.94
  4787.6  876.16  4907.6  867.71  4927.6  867.76  4957.6  863.85  4958.1   858.1
  4959.1   855.1  4996.2   855.1  4997.2   858.1  4997.6  859.21  5017.6  858.49
  5037.6  864.64  5057.6   866.9  5077.6  867.74  5087.6  870.42  5107.6  878.33
  5137.6  885.09  5167.6  888.81  5264.4  893.64  5318.3  895.92  5432.7  895.87
#Mann= 4 ,-1 , 0
  4279.4     .12       0  4958.1     .07       0  4997.2     .12       0
  5264.4     .05       0
Bank Sta=4958.1,4997.2
XS Rating Curve= 0 ,0
Exp/Cntr=0.3,0.1

Type RM Length L Ch R = 1 ,9956    ,599,599,599
BEGIN DESCRIPTION:
WALNUT CREEK 17.0
END DESCRIPTION:
XS GIS Cut Line= 3
      2890724.71     10169820.23      2891088.43     10170154.25
      2891809.25     10170145.59
#Sta/Elev= 30
  4215.8  896.91    4254  896.92    4275  895.24  4282.4  896.81  4317.6  891.27
  4366.9  889.64  4374.3  890.64  4409.4  888.87  4466.2  889.37  4522.9  884.83
  4529.7   886.1  4565.4  882.09  4593.8  879.93  4600.6  880.82  4636.3   877.5
  4786.9  872.29  4876.9     866  4906.9  865.25  4946.9  858.13  4976.9  857.84
  4977.4  854.03  4978.4  851.03  5015.5  851.03  5016.5  854.03  5016.9  859.08
  5026.9  862.63  5076.9  875.11  5116.9  881.49  5274.8  883.03  5430.5  884.92
#Mann= 4 ,-1 , 0
  4215.8     .12       0  4977.4     .07       0  5016.5     .12       0
  5274.8     .05       0
Bank Sta=4977.4,5016.5
XS Rating Curve= 0 ,0
Exp/Cntr=0.3,0.1

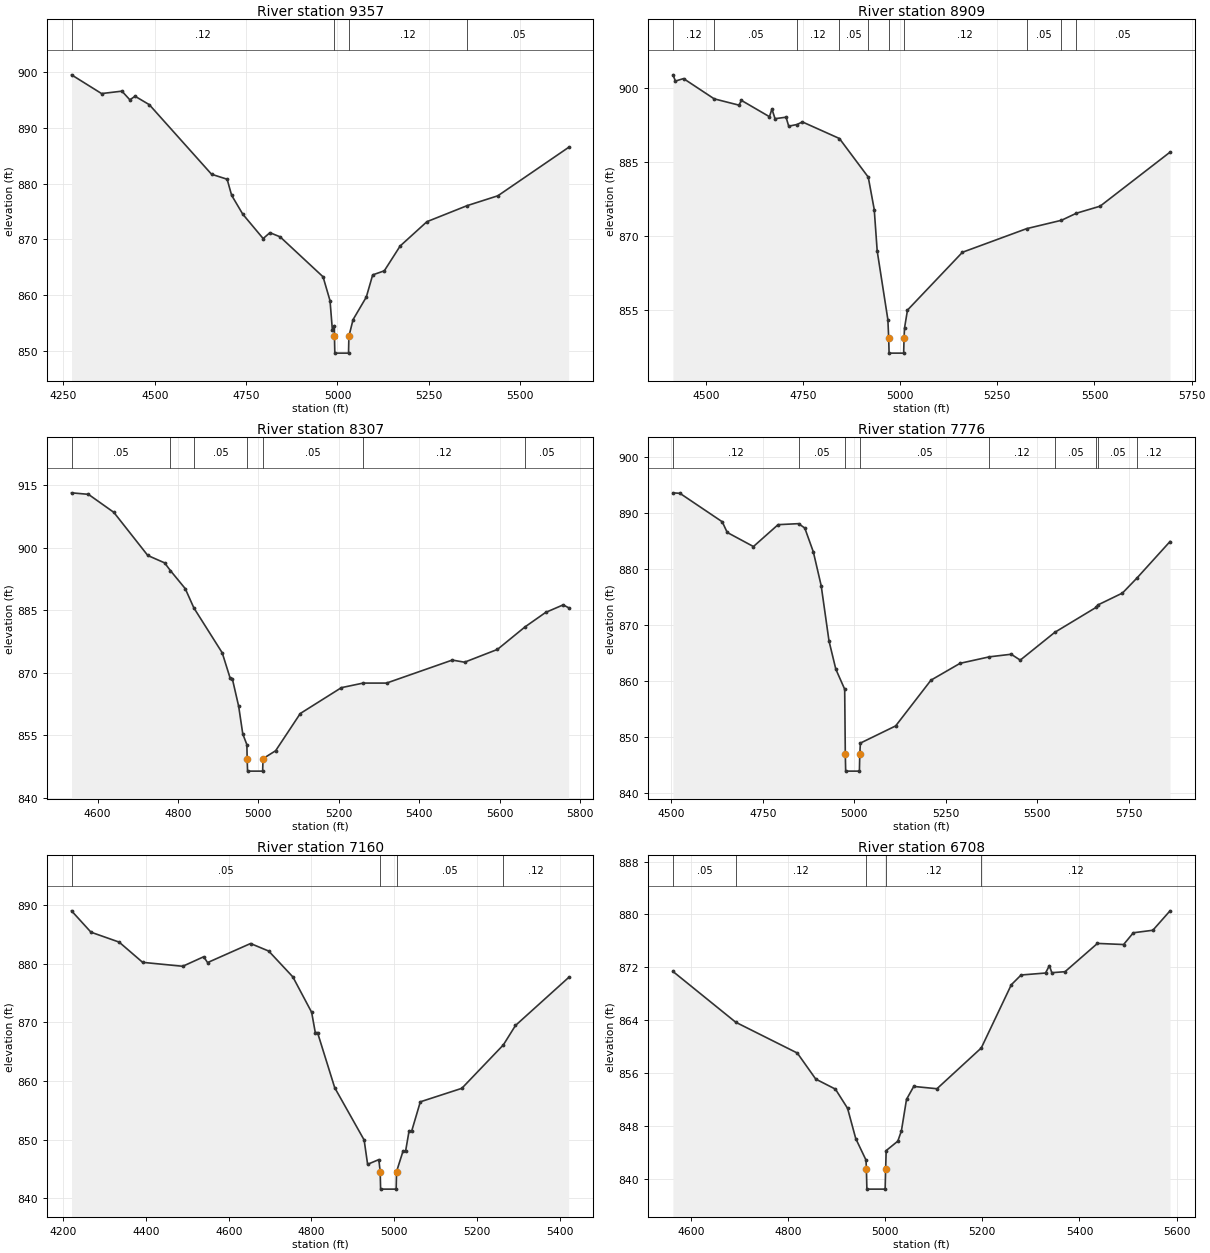
Type RM Length L Ch R = 1 ,9357    ,448,448,448
BEGIN DESCRIPTION:
WALNUT CREEK 16.0
END DESCRIPTION:
XS GIS Cut Line= 3
      2890941.62     10171323.05      2891137.86     10170785.95
       2891881.1     10170522.72
#Sta/Elev= 30
  4272.3  899.44  4354.5  896.09  4410.3  896.52  4431.9  894.97  4446.2  895.61
  4485.2   894.1  4655.5  881.66  4698.1  880.77  4710.4   877.9  4740.9  874.52
  4796.7  870.16  4815.2  871.21    4843  870.47  4960.6  863.32  4979.7  859.04
  4986.2  853.74  4991.5   854.6  4991.8  852.67  4992.8  849.67  5030.3  849.67
  5031.3  852.67  5042.7  855.66  5078.9  859.69  5096.4  863.66  5128.2  864.39
  5171.6  868.83  5244.9  873.18    5355  876.05    5439  877.81  5632.6  886.47
#Mann= 4 ,-1 , 0
  4272.3     .12       0  4991.8     .07       0  5031.3     .12       0
    5355     .05       0
Bank Sta=4991.8,5031.3
XS Rating Curve= 0 ,0
Exp/Cntr=0.3,0.1

Type RM Length L Ch R = 1 ,8909    ,602,602,602
BEGIN DESCRIPTION:
WALNUT CREEK 15.0
END DESCRIPTION:
XS GIS Cut Line= 3
      2890988.08     10171514.12      2891294.37     10171270.02
      2891963.99     10170687.96
#Sta/Elev= 30
  4415.5  902.66    4422   901.4  4442.8   901.9  4521.7   897.8  4585.3  896.53
  4591.7  897.49  4663.8  894.19  4670.2  895.74  4678.2  893.79  4706.5  894.09
  4713.4  892.27  4734.5  892.61  4748.7  893.13  4843.8  889.78    4918  881.97
  4933.4  875.42    4941  867.03  4968.5  853.13  4970.6  849.37  4971.6  846.37
  5009.1  846.37  5010.1  849.37  5011.3  851.43  5018.9  855.07  5160.3  866.77
  5325.6  871.55  5415.1  873.24  5453.6  874.67  5514.5  876.09  5694.4  887.02
#Mann= 10 ,-1 , 0
  4415.5     .12       0  4521.7     .05       0  4734.5     .12       0
  4843.8     .05       0    4918     .12       0  4970.6     .07       0
  5010.1     .12       0  5325.6     .05       0  5415.1     .12       0
  5453.6     .05       0
Bank Sta=4970.6,5010.1
XS Rating Curve= 0 ,0
Exp/Cntr=0.3,0.1

Type RM Length L Ch R = 1 ,8307    ,531,531,531
BEGIN DESCRIPTION:
WALNUT CREEK 14.0
END DESCRIPTION:
XS GIS Cut Line= 3
      2891773.07     10171953.03      2891848.41     10171723.56
      2892051.92     10170749.82
#Sta/Elev= 30
  4535.2  913.13  4577.2  912.77  4640.4  908.45  4724.9   898.1  4766.7  896.33
  4781.1  894.48    4818  890.15  4839.5  885.52    4910  874.75  4929.9  868.61
    4935  868.58  4950.9  861.92  4961.1  855.29  4971.3  852.72    4972  849.37
    4973  846.37  5010.5  846.37  5011.5  849.37  5042.8  851.26  5104.1  860.19
  5206.3  866.39  5260.4  867.49  5318.6  867.49  5482.1  873.01  5512.7   872.5
  5594.5  875.57  5662.9  880.96  5714.3  884.44  5757.9  886.25  5771.5  885.56
#Mann= 7 ,-1 , 0
  4535.2     .05       0  4781.1     .12       0  4839.5     .05       0
    4972     .05       0  5011.5     .05       0  5260.4     .12       0
  5662.9     .05       0
Bank Sta=4972,5011.5
XS Rating Curve= 0 ,0
Exp/Cntr=0.3,0.1

Type RM Length L Ch R = 1 ,7776    ,616,616,616
BEGIN DESCRIPTION:
WALNUT CREEK 13.0
END DESCRIPTION:
XS GIS Cut Line= 3
      2892589.02     10172071.87      2892470.23     10171756.82
      2892105.69     10170803.12
#Sta/Elev= 30
  4504.7  893.63  4523.9  893.54  4639.3  888.46    4653  886.55  4724.6  884.03
  4791.9  887.94  4847.8  888.12  4864.8  887.34  4888.2  883.07  4909.6  877.04
    4931  867.14  4949.6  862.11  4973.8  858.53  4975.5  846.89  4976.5  843.89
    5014  843.89    5015  846.89  5016.7   848.9    5113  851.97  5209.5  860.15
    5289  863.16  5369.2  864.32  5428.6  864.78  5453.3  863.73  5547.7   868.7
  5660.3  873.15    5665  873.58  5732.5  875.72    5772   878.4  5862.4  884.93
#Mann= 9 ,-1 , 0
  4504.7     .12       0  4847.8     .05       0  4975.5     .05       0
    5015     .05       0  5369.2     .12       0  5547.7     .05       0
  5660.3     .12       0    5665     .05       0    5772     .12       0
Bank Sta=4975.5,5015
XS Rating Curve= 0 ,0
Exp/Cntr=0.3,0.1

Type RM Length L Ch R = 1 ,7160    ,452,452,452
BEGIN DESCRIPTION:
WALNUT CREEK 12.0
END DESCRIPTION:
XS GIS Cut Line= 3
      2893027.97     10171684.55      2892749.44     10171165.38
      2892255.65     10170803.09
#Sta/Elev= 30
    4220  888.98    4267  885.34  4335.1  883.65  4391.9   880.2  4488.8  879.53
  4539.4  881.15  4548.9  880.16  4652.8  883.41  4696.7  882.12    4755  877.72
  4800.4  871.69  4809.2  868.24  4814.6  868.24  4856.2  858.83  4927.3  849.92
  4935.7  845.78  4962.8  846.58  4966.1  844.55  4967.1  841.55  5004.7  841.55
  5005.7  844.55  5021.4  848.05  5027.6  848.06    5036  851.51  5042.2  851.44
  5063.1  856.43  5163.4  858.73  5263.8  866.13  5293.1  869.44  5421.6  877.62
#Mann= 4 ,-1 , 0
    4220     .05       0  4966.1     .05       0  5005.7     .05       0
  5263.8     .12       0
Bank Sta=4966.1,5005.7
XS Rating Curve= 0 ,0
Exp/Cntr=0.3,0.1

Type RM Length L Ch R = 1 ,6708    ,580,580,580
BEGIN DESCRIPTION:
WALNUT CREEK 11.0
END DESCRIPTION:
XS GIS Cut Line= 3
      2893155.68     10170753.11      2892576.89     10170575.86
      2892160.52     10170532.92
#Sta/Elev= 30
  4562.7  871.37  4692.1  863.68  4818.9  859.02  4856.9  855.08  4897.4  853.56
  4922.4  850.66  4939.2  846.09  4960.4  842.82  4961.2  841.43  4962.2  838.43
  4999.8  838.43  5000.8  841.43  5001.9  844.26  5025.9  845.69  5033.3  847.25
  5043.8  852.01  5058.7  853.97  5106.5  853.62  5197.8  859.79  5259.7  869.36
  5279.8  870.83  5330.1  871.13  5338.1  872.25  5343.1  871.18  5370.3  871.33
  5437.1  875.61  5490.9  875.44    5511  877.22  5551.2   877.6  5586.6  880.54
#Mann= 5 ,-1 , 0
  4562.7     .05       0  4692.1     .12       0  4961.2     .05       0
  5000.8     .12       0  5197.8     .12       0
Bank Sta=4961.2,5000.8
XS Rating Curve= 0 ,0
Exp/Cntr=0.3,0.1

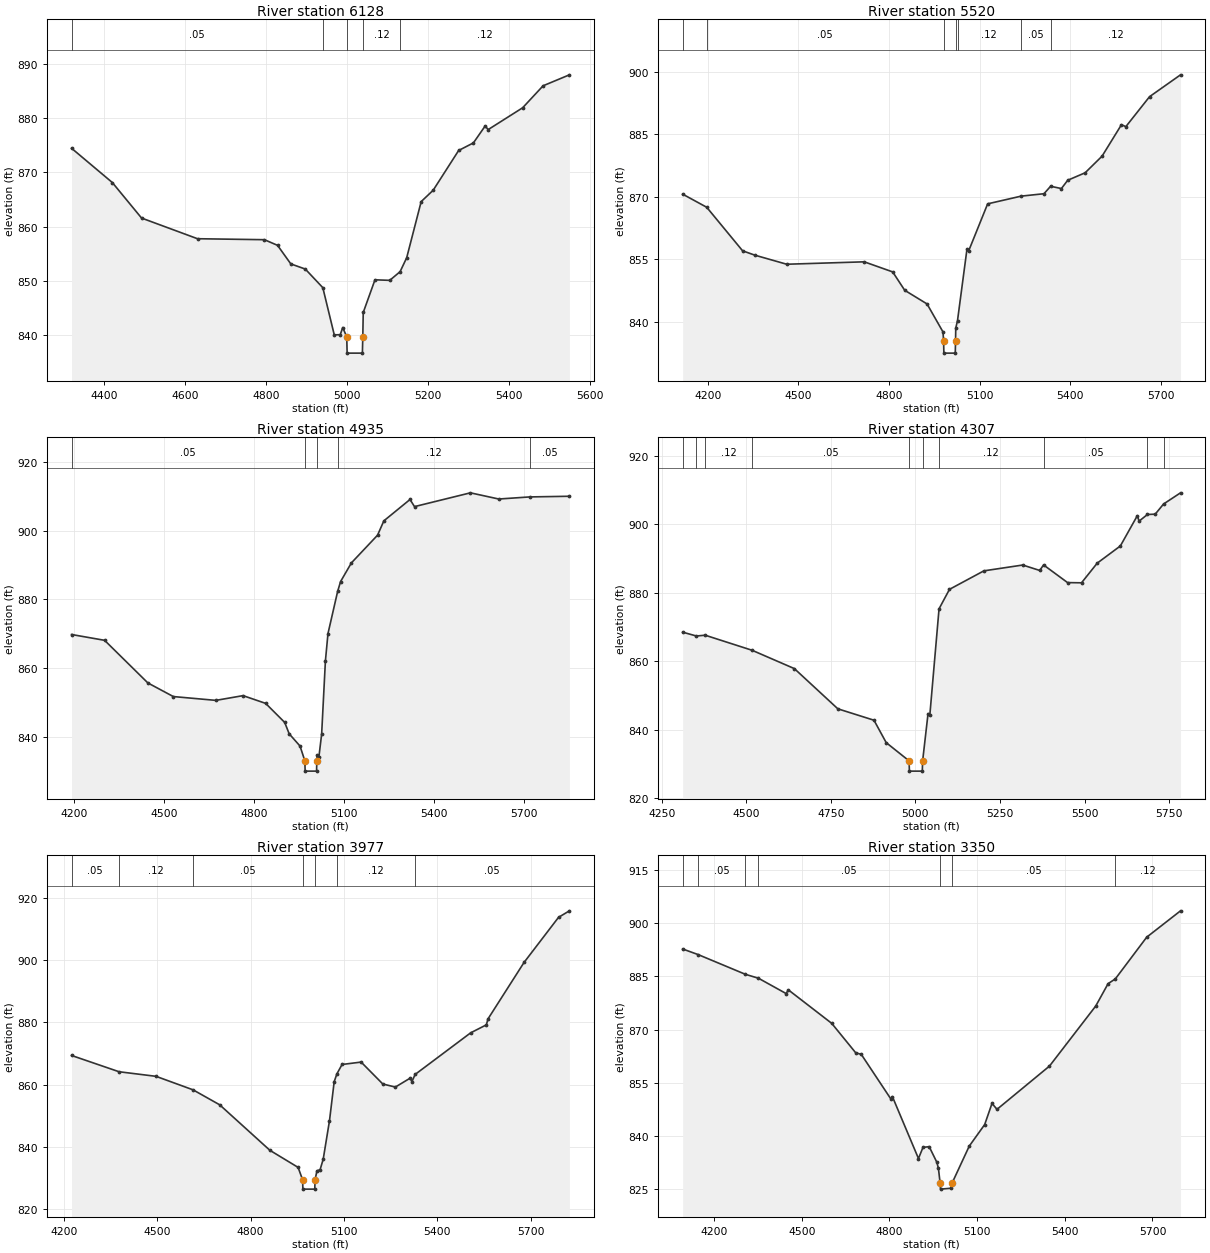
Type RM Length L Ch R = 1 ,6128    ,608,608,608
BEGIN DESCRIPTION:
WALNUT CREEK 10.0
END DESCRIPTION:
XS GIS Cut Line= 3
       2893355.7     10170603.14      2893075.65     10170181.03
      2892480.64     10169768.66
#Sta/Elev= 30
  4319.1  874.44  4419.9  868.12  4492.1  861.58  4630.4  857.77  4795.8  857.59
  4828.2  856.55    4861  853.13  4896.8  852.18  4940.1  848.75  4968.4  840.05
  4983.2  840.09  4989.3  841.41  4999.2  839.69  5000.2  836.69  5037.9  836.69
  5038.9  839.69    5040  844.18    5069   850.2  5105.5   850.1  5131.1   851.7
  5147.4  854.27  5183.2  864.61  5212.9  866.71  5275.8  874.03  5312.3  875.43
  5341.3  878.54  5348.8  877.88    5434   881.9  5484.5  885.95  5549.6  887.97
#Mann= 5 ,-1 , 0
  4319.1     .05       0  4940.1     .12       0  4999.2     .07       0
  5038.9     .12       0  5131.1     .12       0
Bank Sta=4999.2,5038.9
XS Rating Curve= 0 ,0
Exp/Cntr=0.3,0.1

Type RM Length L Ch R = 1 ,5520    ,585,585,585
BEGIN DESCRIPTION:
WALNUT CREEK 9.0
END DESCRIPTION:
XS GIS Cut Line= 3
      2893513.39     10170419.29      2893141.57     10169324.48
      2892837.27     10168937.65
#Sta/Elev= 30
  4116.6  870.59  4196.3  867.44  4315.1  856.99  4355.5  855.95  4461.1  853.77
  4717.8  854.35    4812  851.93  4851.8  847.52  4925.8  844.24  4978.6  837.52
  4980.5  835.44  4981.5  832.44  5019.2  832.44  5020.2  835.44  5020.8  838.44
  5026.6  840.23  5057.8  857.31  5063.1  856.89  5126.4  868.26  5237.2  870.11
  5312.9  870.69  5334.9  872.48  5370.6  871.93  5391.5  873.92  5449.3  875.72
  5505.3  879.71  5569.5  887.26  5583.9  886.78  5662.5  893.98    5765  899.22
#Mann= 7 ,-1 , 0
  4116.6     .12       0  4196.3     .05       0  4980.5     .05       0
  5020.2     .05       0  5026.6     .12       0  5237.2     .05       0
  5334.9     .12       0
Bank Sta=4980.5,5020.2
XS Rating Curve= 0 ,0
Exp/Cntr=0.3,0.1

Type RM Length L Ch R = 1 ,4935    ,628,628,628
BEGIN DESCRIPTION:
WALNUT CREEK 8.0
END DESCRIPTION:
XS GIS Cut Line= 3
      2893596.02     10170409.01      2893683.82      10169768.6
      2894246.31     10168927.44
#Sta/Elev= 30
  4192.6  869.81  4302.6  868.12  4446.8  855.72  4531.6  851.76  4673.3  850.65
  4763.8  852.03    4839  849.78  4902.5  844.24  4917.5  840.92  4953.6  837.36
  4969.6  833.07  4970.6  830.07  5008.6  830.07  5009.6  833.07  5010.6  834.62
  5016.6   834.3  5025.6  840.85  5038.1  862.11  5046.7  870.09  5078.8  882.33
  5088.7  885.22  5124.7  890.64  5211.8   898.7  5232.8  902.87  5319.9  909.08
  5334.9  907.01  5521.1  911.02  5615.5  909.22    5719  909.83  5850.9  910.02
#Mann= 5 ,-1 , 0
  4192.6     .05       0  4969.6     .05       0  5009.6     .05       0
  5078.8     .12       0    5719     .05       0
Bank Sta=4969.6,5009.6
XS Rating Curve= 0 ,0
Exp/Cntr=0.3,0.1

Type RM Length L Ch R = 1 ,4307    ,330,330,330
BEGIN DESCRIPTION:
WALNUT CREEK 7.0
END DESCRIPTION:
XS GIS Cut Line= 3
      2893606.39     10170460.57      2893935.72     10170156.15
      2894928.21     10169908.08
#Sta/Elev= 30
    4312  868.54  4352.6  867.42  4378.6  867.65  4517.3  863.25  4642.2   857.9
  4770.7  846.16  4877.5  842.83  4913.6  836.29  4981.2  830.97  4982.2  827.97
  5020.3  827.97  5021.3  830.97  5037.3  844.77  5042.5  844.25  5069.8  875.36
  5100.6  881.04  5202.3  886.44  5317.1  888.14  5367.2  886.56  5378.8  888.16
  5449.7  883.01  5490.9  882.95  5537.3  888.69  5605.7  893.71  5655.9  902.56
    5661  900.95  5685.8   902.9  5708.7  902.99  5733.4  905.96  5783.5  909.22
#Mann= 10 ,-1 , 0
    4312     .12       0  4352.6     .05       0  4378.6     .12       0
  4517.3     .05       0  4981.2     .05       0  5021.3     .05       0
  5069.8     .12       0  5378.8     .05       0  5685.8     .12       0
  5733.4     .05       0
Bank Sta=4981.2,5021.3
XS Rating Curve= 0 ,0
Exp/Cntr=0.3,0.1

Type RM Length L Ch R = 1 ,3977    ,627,627,627
BEGIN DESCRIPTION:
WALNUT CREEK 6.0
END DESCRIPTION:
XS GIS Cut Line= 3
      2893435.91     10170641.36      2893850.41      10170465.9
      2894990.39     10170326.33
#Sta/Elev= 30
  4225.4  869.36  4377.9  864.14  4496.6  862.67  4615.5  858.34    4701  853.54
  4862.2  838.95  4952.8  833.47  4967.2   829.5  4968.2   826.5  5006.3   826.5
  5007.3   829.5  5013.3  832.35  5023.4  832.73  5033.4  836.08  5053.6  848.45
  5068.7  860.96  5077.5  863.48  5093.9  866.47  5155.2  867.24  5224.9   860.2
  5265.1  859.23    5313  862.11  5318.1  860.94  5328.6  863.28  5506.9  876.62
  5557.3  879.18  5562.4  881.06  5678.2  899.18    5789  913.65    5824  915.74
#Mann= 7 ,-1 , 0
  4225.4     .05       0  4377.9     .12       0  4615.5     .05       0
  4967.2     .05       0  5007.3     .05       0  5077.5     .12       0
  5328.6     .05       0
Bank Sta=4967.2,5007.3
XS Rating Curve= 0 ,0
Exp/Cntr=0.3,0.1

Type RM Length L Ch R = 1 ,3350    ,469,469,469
BEGIN DESCRIPTION:
WALNUT CREEK 5.0
END DESCRIPTION:
XS GIS Cut Line= 3
      2893477.23     10171514.12      2893890.38     10171162.94
       2894990.4      10170791.1
#Sta/Elev= 30
  4092.6   892.7  4145.8  891.11  4307.6  885.55  4351.8  884.46  4446.5  880.14
  4454.3  881.17  4602.5  871.75  4684.5  863.46  4703.8  862.99  4805.1  850.41
  4810.3  851.08  4899.4  833.65  4914.9  836.78  4936.1  836.99  4962.3  832.59
  4967.7  830.89  4973.6  826.61 4974.83  825.02 5012.39  825.28  5013.8  826.61
  5073.2  837.15    5126  843.22    5151  849.17  5168.2  847.51  5347.7   859.7
    5506  876.63  5548.2  882.93  5572.8  884.25  5680.3  896.02    5796  903.45
#Mann= 7 ,-1 , 0
  4092.6     .12       0  4145.8     .05       0  4307.6     .12       0
  4351.8     .05       0  4973.6     .05       0  5013.8     .05       0
  5572.8     .12       0
Bank Sta=4973.6,5013.8
XS Rating Curve= 0 ,0
Exp/Cntr=0.3,0.1

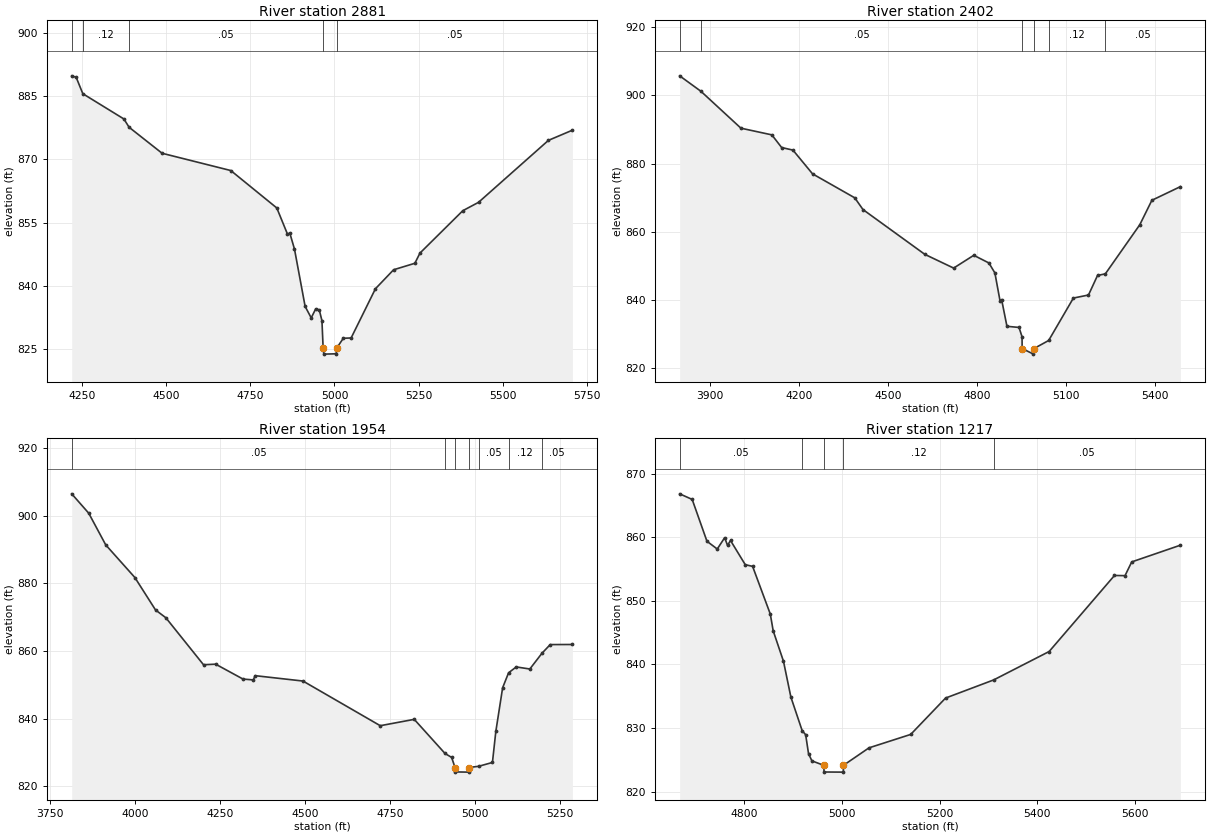
Type RM Length L Ch R = 1 ,2881    ,479,479,479
BEGIN DESCRIPTION:
WALNUT CREEK 4.0
END DESCRIPTION:
XS GIS Cut Line= 3
      2893626.99     10171792.98      2894029.82      10171601.9
      2895020.97     10171276.67
#Sta/Elev= 30
  4218.7  889.86    4232  889.51  4251.8  885.61  4373.9  879.61  4389.4  877.64
  4487.6  871.46  4691.8  867.36  4828.6  858.47  4860.2  852.28  4867.3   852.5
  4881.2  848.69  4912.8  835.09  4930.9  832.36  4944.4  834.52  4954.9  834.25
  4962.8  831.72  4966.4  825.17 4968.64  823.75  5005.2  823.83  5006.6  825.17
  5026.4  827.52  5049.6  827.59  5121.9  839.28  5175.9  843.79  5239.1  845.33
  5254.4  847.76  5381.7  857.82  5428.5  859.81  5636.3  874.53  5707.7  876.95
#Mann= 5 ,-1 , 0
  4218.7     .05       0  4251.8     .12       0  4389.4     .05       0
  4966.4     .05       0  5006.6     .05       0
Bank Sta=4966.4,5006.6
XS Rating Curve= 0 ,0
Exp/Cntr=0.3,0.1

Type RM Length L Ch R = 1 ,2402    ,448,448,448
BEGIN DESCRIPTION:
WALNUT CREEK 3.0
END DESCRIPTION:
XS GIS Cut Line= 3
      2893342.99     10172257.75      2894164.96     10172010.01
      2894980.05     10171854.94
#Sta/Elev= 30
  3798.4  905.76  3870.2  901.22    4005   890.4  4109.2  888.44  4142.2  884.73
  4180.4  883.97  4246.4  877.01  4388.8  869.97  4416.5  866.53    4625  853.39
  4722.2  849.36    4790  853.11  4840.9  850.87  4861.2  847.95  4878.8  839.63
  4883.9  840.12  4901.9  832.28  4942.6  831.95  4952.8   829.2  4953.1  825.77
 4991.28  824.12  4993.3  825.77  5042.5  828.12  5125.9  840.57  5176.8  841.46
  5207.3   847.2  5233.6  847.67  5349.8  862.08  5390.5  869.25  5486.6  873.25
#Mann= 6 ,-1 , 0
  3798.4     .12       0  3870.2     .05       0  4953.1     .03       0
  4993.3     .05       0  5042.5     .12       0  5233.6     .05       0
Bank Sta=4953.1,4993.3
XS Rating Curve= 0 ,0
Exp/Cntr=0.3,0.1

Type RM Length L Ch R = 1 ,1954    ,737,737,737
BEGIN DESCRIPTION:
WALNUT CREEK 2.0
END DESCRIPTION:
XS GIS Cut Line= 3
      2893430.74     10172624.42      2894070.14     10172386.88
      2894860.94     10172386.86
#Sta/Elev= 30
  3813.3  906.45  3863.4  900.72  3913.4  891.35  3999.1   881.7  4059.9   872.1
  4090.2   869.8    4201   855.9  4236.7  856.07  4317.1  851.67  4347.5  851.41
  4352.8  852.67  4493.6  851.08  4720.9  837.87  4820.9  839.75  4911.5  829.65
  4930.9  828.49  4940.8   825.5 4941.75   824.2  4980.9  824.14    4981   825.5
  5010.2  825.86  5050.9     827  5060.9   836.2  5080.9   849.1  5098.4  853.52
  5120.9  855.25  5160.9  854.64  5196.7  859.31  5220.9  861.86  5286.2  861.89
#Mann= 7 ,-1 , 0
  3813.3     .05       0  4911.5     .12       0  4940.8     .07       0
    4981     .12       0  5010.2     .05       0  5098.4     .12       0
  5196.7     .05       0
Bank Sta=4940.8,4981
XS Rating Curve= 0 ,0
Exp/Cntr=0.3,0.1

Type RM Length L Ch R = 1 ,1217    ,0,0,0
BEGIN DESCRIPTION:
WALNUT CREEK 1.0
END DESCRIPTION:
XS GIS Cut Line= 3
       2894317.3     10173350.62      2894644.36     10172846.47
      2894855.09     10172476.41
#Sta/Elev= 30
  4667.1  866.82  4692.8  865.94  4723.1  859.36  4744.2  858.14  4759.4  859.92
  4765.3  858.71  4771.4  859.48  4801.6  855.68  4816.7  855.41    4853  847.91
  4858.9  845.28    4880  840.49  4895.2  834.85  4918.3  829.58  4925.5  828.93
  4931.4  825.95  4938.3  824.82  4962.7  824.12 4963.22  823.07 5002.76  823.05
    5003  824.12  5055.4  826.87  5140.9  828.98  5212.4   834.7    5311  837.55
  5424.8  842.02  5558.8  853.98  5580.4  853.95  5594.1  856.11  5693.9  858.74
#Mann= 5 ,-1 , 0
  4667.1     .05       0  4918.3     .12       0  4962.7     .07       0
    5003     .12       0    5311     .05       0
Bank Sta=4962.7,5003
XS Rating Curve= 0 ,0
Exp/Cntr=0.3,0.1

Chan Stop Cuts=-1
Use User Specified Reach Order=0
Composite Channel Slope=5