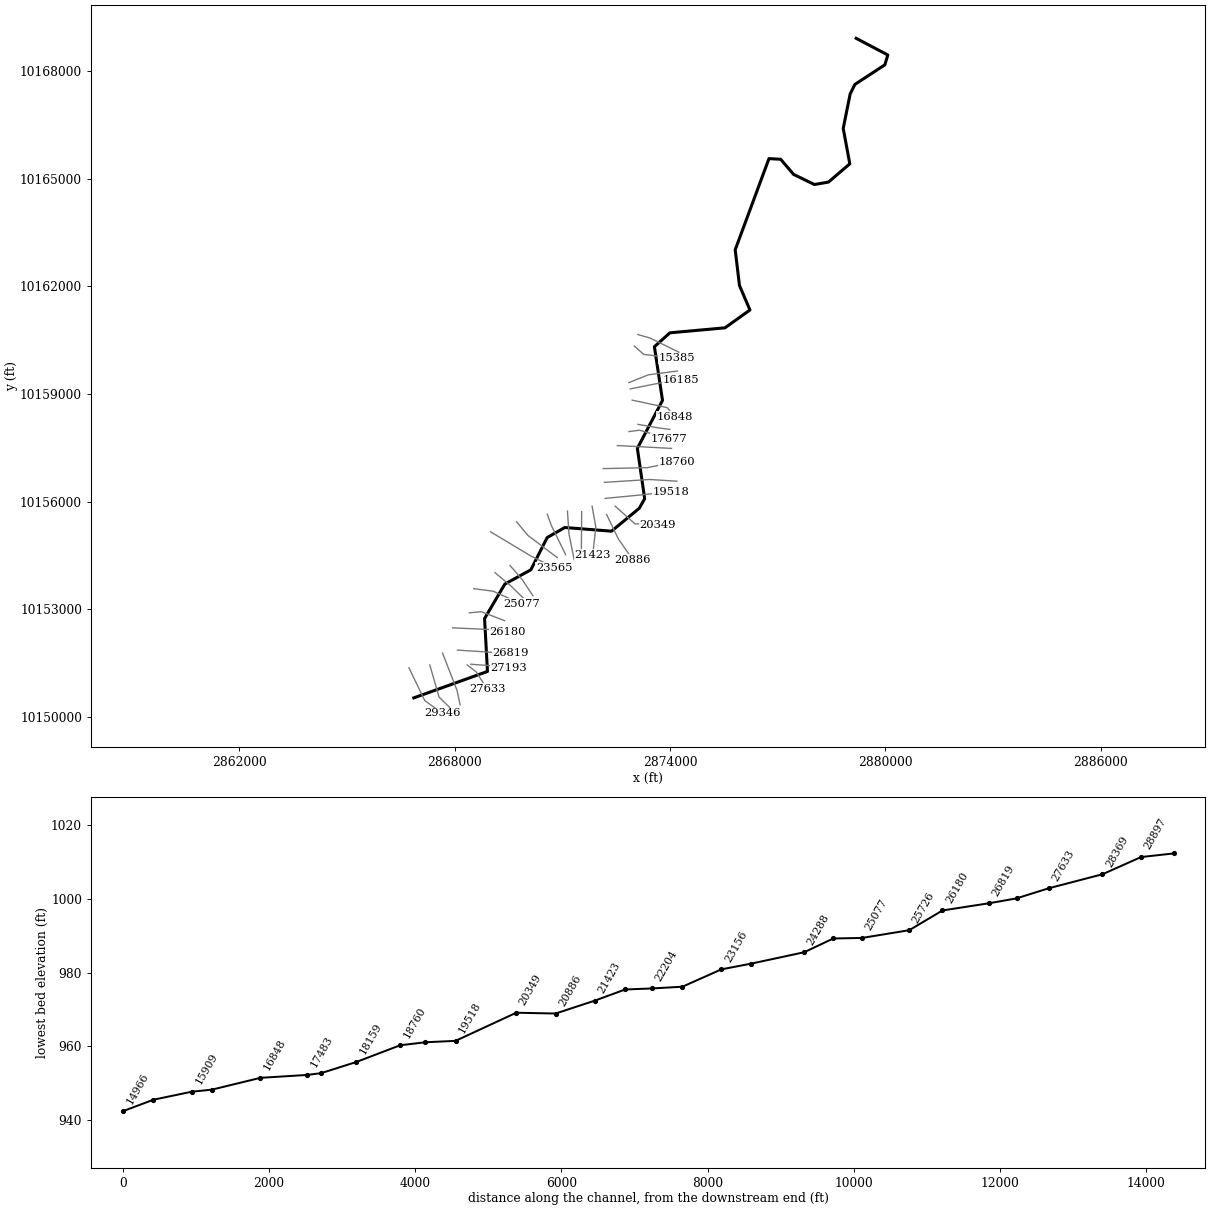
--- WHITE CREEK.prj (project) ---

Proj Title=WHITE CREEK Base Level Engineering
Current Plan=p01
Default Exp/Contr=0.3,0.1
English Units
Geom File=g01
Flow File=f01
Plan File=p01
BEGIN DESCRIPTION:
WHITE CREEK
END DESCRIPTION:

--- WHITE CREEK.p01 (plan) ---

Plan Title=Multiple Run
Short Identifier=Multiple
Geom File=g01
Flow File=f01
Subcritical Flow
K Sum by GR= 0
Std Step Tol= 0.01
Critical Tol= 0.01
Num of Std Step Trials= 20
Max Error Tol= 0.3
Flow Tol Ratio= 0.001
Split Flow NTrial= 30
Split Flow Tol= 0.02
Split Flow Ratio= 0.02
Log Output Level= 0
Friction Slope Method= 1
Unsteady Friction Slope Method= 2
Unsteady Bridges Friction Slope Method= 1
Parabolic Critical Depth
Global Vel Dist=  1 , 1 , 1
Global Log Level= 0
CheckData=True
Encroach Param= -1, 0, 0, 0
BEGIN DESCRIPTION:
Multiple Run
END DESCRIPTION:

--- WHITE CREEK.f01 (steady flow) ---

Flow Title=Multiple
Number of Profiles=7
Profile Names=10-year,25-year,50-year,1pct_min,100-year,1pct_plu,500-year
River Rch & RM= WHITE CREEK,Reach-1,29346
     560    1304    2240    1257    3795   11461   11548
River Rch & RM= WHITE CREEK,Reach-1,25077
     580    1353    2326    1307    3946   11916   12026
River Rch & RM= WHITE CREEK,Reach-1,20886
     615    1439    2478    1393    4208   12708   12860
River Rch & RM= WHITE CREEK,Reach-1,18159
     643    1506    2596    1462    4414   13329   13514
River Rch & RM= WHITE CREEK,Reach-1,16848
     688    1618    2795    1576    4759   14371   14614
River Rch & RM= WHITE CREEK,Reach-1,9956
     701    1650    2852    1609    4858   14670   14929
River Rch & RM= WHITE CREEK,Reach-1,2537
     760    1794    3107    1756    5302   16013   16350
Boundary for River Rch & Prof#=WHITE CREEK,Reach-1,1
Up Type=0
Dn Type=3
Dn Slope=0.005
Boundary for River Rch & Prof#=WHITE CREEK,Reach-1,2
Up Type=0
Dn Type=3
Dn Slope=0.005
Boundary for River Rch & Prof#=WHITE CREEK,Reach-1,3
Up Type=0
Dn Type=3
Dn Slope=0.005
Boundary for River Rch & Prof#=WHITE CREEK,Reach-1,4
Up Type=0
Dn Type=3
Dn Slope=0.005
Boundary for River Rch & Prof#=WHITE CREEK,Reach-1,5
Up Type=0
Dn Type=3
Dn Slope=0.005
Boundary for River Rch & Prof#=WHITE CREEK,Reach-1,6
Up Type=0
Dn Type=3
Dn Slope=0.005
Boundary for River Rch & Prof#=WHITE CREEK,Reach-1,7
Up Type=0
Dn Type=3
Dn Slope=0.005

--- WHITE CREEK.g01 (geometry) ---

Geom Title=Existing Conditions

River Reach=WHITE CREEK,Reach-1
Reach XY= 30
      2866862.25     10150535.00      2868913.00     10151271.00
      2868832.00     10152744.00      2869396.00     10153704.00
      2870121.25     10154103.00      2870576.00     10155001.00
      2871067.00     10155281.00      2872368.00     10155178.00
      2873142.25     10155817.00      2873292.00     10156083.00
      2873088.00     10157486.00      2873788.50     10158822.00
      2873563.00     10160317.00      2873995.00     10160704.00
      2875529.50     10160843.00      2876224.50     10161340.00
      2875932.50     10162022.00      2875813.50     10163017.00
      2876754.75     10165557.00      2877080.25     10165538.00
      2877439.50     10165117.00      2878019.50     10164835.00
      2878412.00     10164903.00      2879005.75     10165411.00
      2878822.50     10166397.00      2879015.75     10167357.00
      2879147.50     10167623.00      2879982.75     10168169.00
      2880064.25     10168443.00      2879183.75     10168907.00

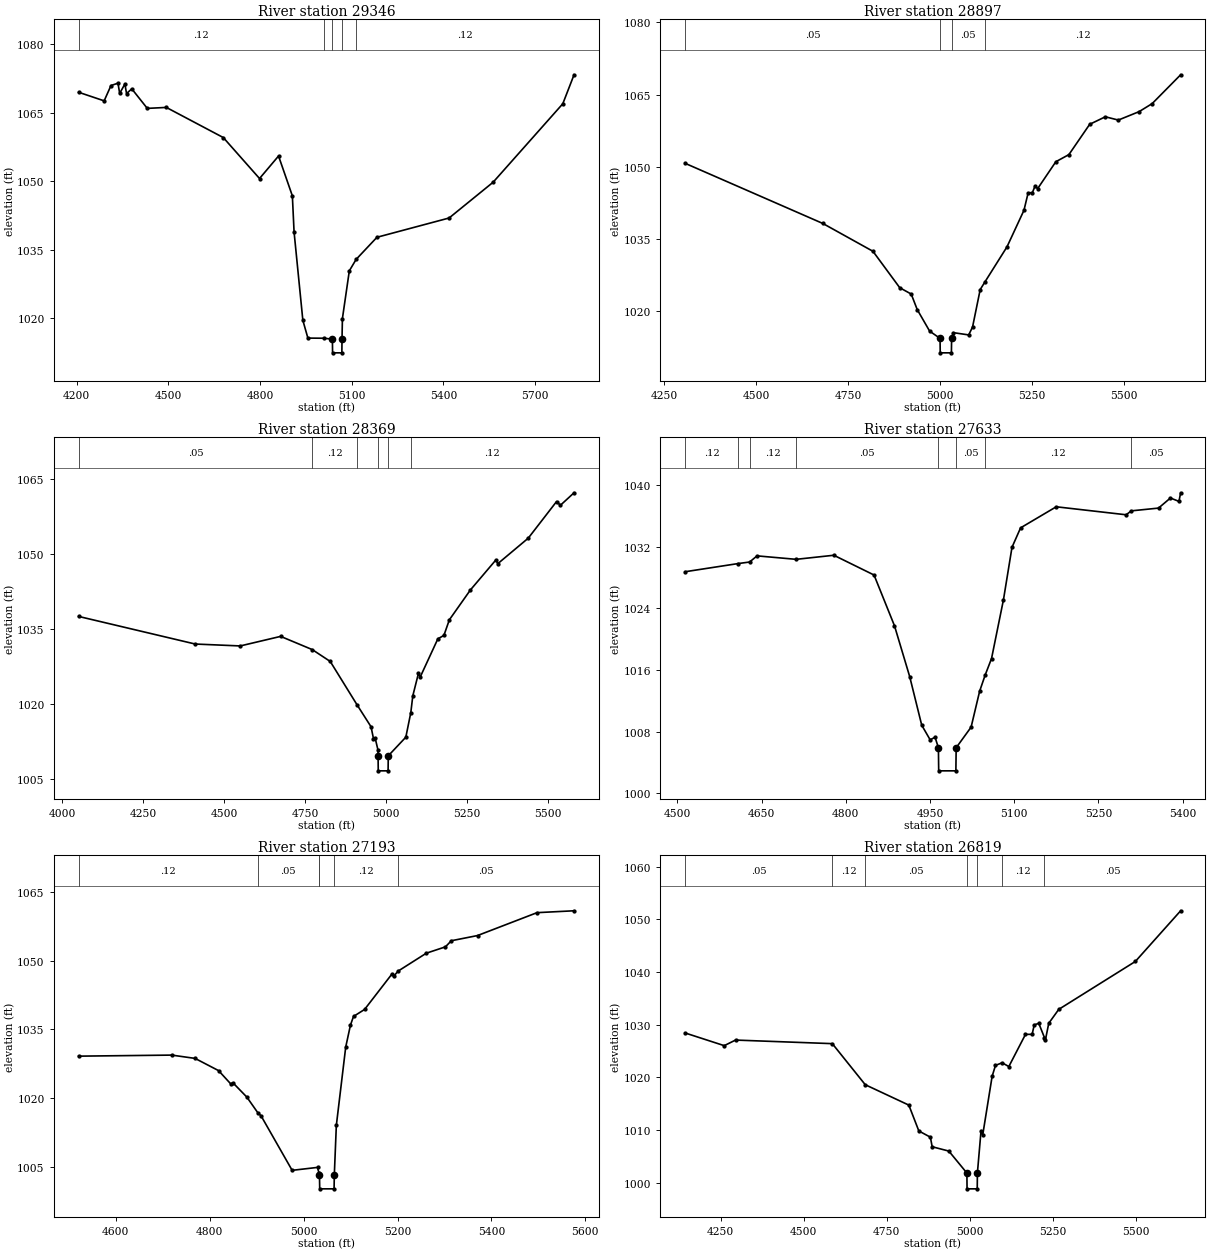
Type RM Length L Ch R = 1,29346,449,449,449
BEGIN DESCRIPTION:
WHITE CREEK 54.0
END DESCRIPTION:
XS GIS Cut Line= 3
      2866724.39     10151373.41      2867165.39     10150461.21
      2867655.72     10150103.08
#Sta/Elev= 30
  4206.9 1069.44  4290.4 1067.56  4312.7 1070.91  4335.6 1071.43  4341.2 1069.19
  4358.2 1071.25  4363.7 1069.16  4380.8 1070.19  4431.5 1065.91  4493.8 1066.12
  4680.1 1059.52  4798.6 1050.55  4860.8 1055.48  4906.0 1046.75  4911.6 1038.83
  4940.3 1019.49  4956.8 1015.60  5008.3 1015.57  5037.0 1015.37  5037.5 1012.37
  5067.9 1012.37  5068.4 1015.37  5069.7 1019.88  5092.3 1030.33  5114.6 1032.84
  5182.7 1037.68  5418.6 1041.90  5562.7 1049.74  5790.6 1066.93  5827.3 1073.27
#Mann=5,-1,0
  4206.9    0.12       0  5008.3    0.05       0  5037.0    0.07       0
  5068.4    0.05       0  5114.6    0.12       0
Bank Sta=5037,5068.4
Exp/Cntr=0.3,0.1

Type RM Length L Ch R = 1,28897,528,528,528
BEGIN DESCRIPTION:
WHITE CREEK 53.0
END DESCRIPTION:
XS GIS Cut Line= 3
      2867305.70     10151453.07      2867564.08     10150557.86
      2867860.00     10150267.98
#Sta/Elev= 30
  4307.4 1050.71  4681.4 1038.23  4817.4 1032.46  4890.2 1024.90  4921.4 1023.58
  4937.7 1020.36  4971.4 1015.89  4999.7 1014.38  5000.2 1011.38  5030.6 1011.38
  5031.1 1014.38  5035.9 1015.57  5077.5 1015.10  5088.0 1016.73  5108.8 1024.52
  5122.0 1026.14  5181.6 1033.38  5227.7 1040.97  5239.0 1044.57  5250.7 1044.66
  5257.7 1045.98  5264.9 1045.47  5314.3 1051.05  5349.8 1052.53  5406.3 1058.82
  5448.8 1060.38  5484.1 1059.70  5540.6 1061.45  5576.1 1063.12  5653.4 1069.10
#Mann=4,-1,0
  4307.4    0.05       0  4999.7    0.05       0  5031.1    0.05       0
  5122.0    0.12       0
Bank Sta=4999.7,5031.1
Exp/Cntr=0.3,0.1

Type RM Length L Ch R = 1,28369,736,736,736
BEGIN DESCRIPTION:
WHITE CREEK 52.0
END DESCRIPTION:
XS GIS Cut Line= 3
      2867660.75     10151784.11      2868064.71     10150743.49
      2868150.04     10150340.40
#Sta/Elev= 30
  4051.6 1037.58  4411.3 1032.06  4550.2 1031.68  4674.8 1033.59  4772.3 1030.95
  4827.8 1028.58  4910.2 1019.94  4953.7 1015.52  4961.2 1013.14  4966.6 1013.20
  4975.2 1010.84  4975.4 1009.71  4975.9 1006.71  5006.3 1006.71  5006.8 1009.71
  5061.0 1013.44  5076.4 1018.37  5082.5 1021.70  5100.0 1026.22  5105.4 1025.47
  5159.8 1033.10  5178.5 1033.79  5195.3 1036.91  5260.3 1042.88  5339.3 1048.91
  5344.4 1048.11  5438.7 1053.23  5526.0 1060.55  5538.0 1059.81  5579.9 1062.30
#Mann=6,-1,0
  4051.6    0.05       0  4772.3    0.12       0  4910.2    0.05       0
  4975.4    0.05       0  5006.8    0.05       0  5076.4    0.12       0
Bank Sta=4975.4,5006.8
Exp/Cntr=0.3,0.1

Type RM Length L Ch R = 1,27633,440,440,440
BEGIN DESCRIPTION:
WHITE CREEK 51.0
END DESCRIPTION:
XS GIS Cut Line= 3
      2868346.16     10151453.75      2868601.68     10151255.73
      2868901.29     10150784.00
#Sta/Elev= 30
  4514.2 1028.78  4608.4 1029.84  4628.8 1030.04  4642.1 1030.84  4711.7 1030.39
  4778.8 1030.92  4850.4 1028.35  4886.8 1021.75  4913.9 1015.14  4935.3 1008.83
  4950.3 1006.93  4959.0 1007.27  4965.0 1005.90  4965.5 1002.90  4996.1 1002.90
  4996.6 1005.90  5023.2 1008.58  5038.4 1013.25  5048.2 1015.34  5059.6 1017.50
  5080.8 1025.13  5096.0 1031.95  5111.3 1034.48  5174.8 1037.22  5299.3 1036.18
  5308.4 1036.69  5356.9 1037.05  5378.1 1038.36  5393.3 1037.92  5396.3 1039.04
#Mann=8,-1,0
  4514.2    0.12       0  4608.4    0.05       0  4628.8    0.12       0
  4711.7    0.05       0  4965.0    0.05       0  4996.6    0.05       0
  5048.2    0.12       0  5308.4    0.05       0
Bank Sta=4965,4996.6
Exp/Cntr=0.3,0.1

Type RM Length L Ch R = 1,27193,374,374,374
BEGIN DESCRIPTION:
WHITE CREEK 50.0
END DESCRIPTION:
XS GIS Cut Line= 3
      2868448.41     10151472.91      2869074.37     10151425.01
      2869495.96     10151354.74
#Sta/Elev= 30
  4520.8 1029.13  4719.2 1029.36  4768.8 1028.64  4818.9 1025.97  4844.9 1023.06
  4849.9 1023.27  4879.1 1020.19  4902.5 1016.77  4909.2 1016.13  4975.6 1004.20
  5029.6 1004.84  5032.6 1003.64  5033.8 1003.16  5034.3 1000.16  5064.9 1000.16
  5065.4 1003.16  5069.7 1014.00  5089.7 1031.12  5099.8 1035.92  5106.3 1037.80
  5129.9 1039.33  5188.0 1047.04  5193.0 1046.71  5201.3 1047.70  5261.4 1051.61
  5302.0 1052.99  5314.7 1054.33  5370.4 1055.46  5497.2 1060.46  5576.0 1060.87
#Mann=6,-1,0
  4520.8    0.12       0  4902.5    0.05       0  5032.6    0.12       0
  5033.8    0.05       0  5065.4    0.12       0  5201.3    0.05       0
Bank Sta=5033.8,5065.4
Exp/Cntr=0.3,0.1

Type RM Length L Ch R = 1,26819,639,639,639
BEGIN DESCRIPTION:
WHITE CREEK 49.0
END DESCRIPTION:
XS GIS Cut Line= 3
      2868074.67     10151865.77      2869109.51     10151798.69
      2869561.89     10151779.58
#Sta/Elev= 30
  4143.8 1028.43  4261.1 1026.03  4295.1 1027.09  4586.1 1026.41  4685.2 1018.61
  4816.2 1014.74  4846.3 1009.83  4881.0 1008.65  4886.4 1006.83  4936.5 1006.01
  4990.8 1001.84  4991.3  998.84  5021.9  998.84  5022.4 1001.84  5033.4 1009.90
  5038.4 1009.07  5066.7 1020.21  5076.8 1022.28  5096.7 1022.78  5116.9 1022.06
  5167.0 1028.17  5187.0 1028.18  5193.3 1029.97  5207.0 1030.27  5224.0 1027.56
  5227.0 1027.15  5237.0 1030.28  5267.1 1032.92  5497.3 1042.01  5633.6 1051.64
#Mann=7,-1,0
  4143.8    0.05       0  4586.1    0.12       0  4685.2    0.05       0
  4990.8    0.05       0  5022.4    0.05       0  5096.7    0.12       0
  5224.0    0.05       0
Bank Sta=4990.8,5022.4
Exp/Cntr=0.3,0.1

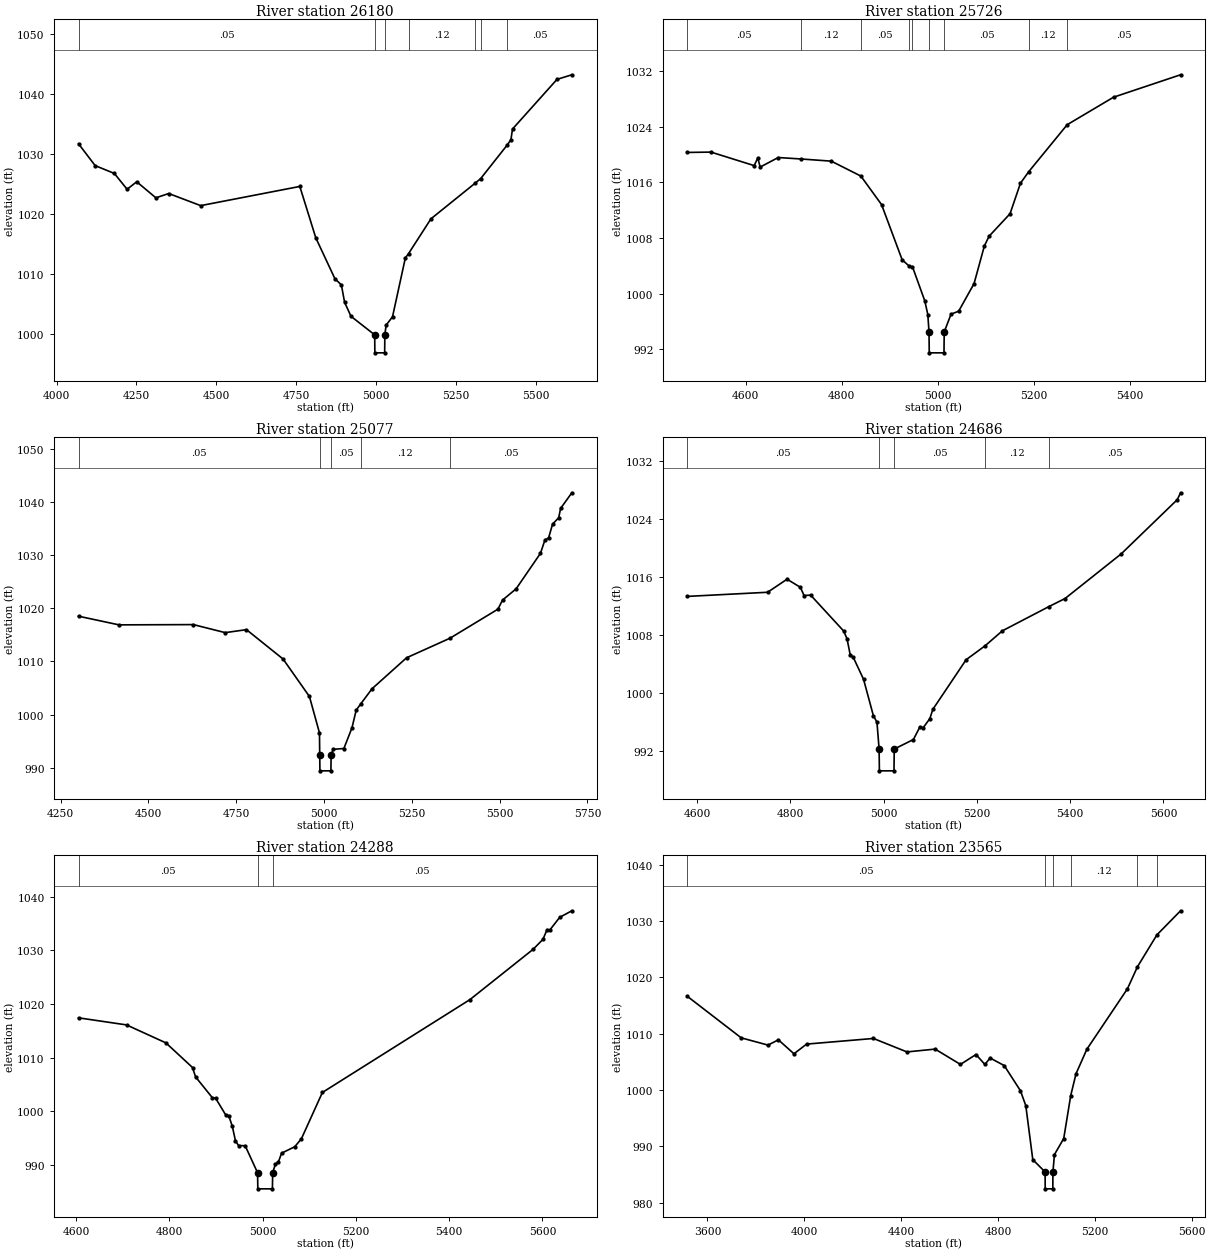
Type RM Length L Ch R = 1,26180,454,454,454
BEGIN DESCRIPTION:
WHITE CREEK 48.0
END DESCRIPTION:
XS GIS Cut Line= 3
      2867943.69     10152485.39      2869029.66     10152437.47
      2869481.92     10152370.59
#Sta/Elev= 30
  4068.6 1031.76  4120.6 1028.12  4180.7 1026.81  4220.7 1024.17  4250.8 1025.42
  4310.8 1022.74  4350.9 1023.46  4451.0 1021.44  4761.3 1024.64  4811.3 1016.07
  4871.4 1009.22  4891.4 1008.22  4901.4 1005.33  4921.4 1002.98  4995.7  999.88
  4996.2  996.88  5026.9  996.88  5027.4  999.88  5031.5 1001.50  5051.5 1002.90
  5091.6 1012.70  5101.7 1013.44  5171.8 1019.24  5309.8 1025.17  5327.3 1025.94
  5410.2 1031.53  5422.1 1032.44  5427.1 1034.22  5566.3 1042.50  5612.8 1043.27
#Mann=7,-1,0
  4068.6    0.05       0  4995.7    0.05       0  5027.4    0.05       0
  5101.7    0.12       0  5309.8    0.05       0  5327.3    0.12       0
  5410.2    0.05       0
Bank Sta=4995.7,5027.4
Exp/Cntr=0.3,0.1

Type RM Length L Ch R = 1,25726,649,649,649
BEGIN DESCRIPTION:
WHITE CREEK 47.0
END DESCRIPTION:
XS GIS Cut Line= 3
      2868406.86     10152903.79      2868739.01     10152935.72
      2869387.41     10152686.59
#Sta/Elev= 30
  4478.0 1020.29  4527.6 1020.34  4617.5 1018.40  4625.1 1019.49  4630.1 1018.19
  4667.7 1019.56  4715.6 1019.35  4778.2 1019.04  4839.9 1016.90  4883.1 1012.80
  4926.0 1004.88  4941.0 1003.95  4947.5 1003.88  4973.2  998.98  4979.5  997.02
  4982.0  994.52  4982.5  991.52  5013.2  991.52  5013.7  994.52  5027.9  997.07
  5043.8  997.50  5075.9 1001.46  5097.4 1006.87  5107.2 1008.26  5150.9 1011.49
  5172.6 1015.87  5189.9 1017.53  5270.0 1024.27  5366.6 1028.22  5506.3 1031.44
#Mann=9,-1,0
  4478.0    0.05       0  4715.6    0.12       0  4839.9    0.05       0
  4941.0    0.12       0  4947.5    0.05       0  4982.0    0.05       0
  5013.7    0.05       0  5189.9    0.12       0  5270.0    0.05       0
Bank Sta=4982,5013.7
Exp/Cntr=0.3,0.1

Type RM Length L Ch R = 1,25077,391,391,391
BEGIN DESCRIPTION:
WHITE CREEK 46.0
END DESCRIPTION:
XS GIS Cut Line= 3
      2868531.39     10153577.70      2869067.99     10153507.43
      2869855.69     10153153.11
#Sta/Elev= 30
  4300.8 1018.49  4416.1 1016.86  4627.9 1016.91  4718.6 1015.40  4779.1 1015.96
  4883.3 1010.44  4958.4 1003.39  4987.0  996.54  4987.7  992.41  4988.3  989.41
  5019.6  989.41  5020.1  992.41  5025.9  993.46  5056.5  993.61  5079.6  997.51
  5091.6 1000.82  5104.0 1001.96  5136.9 1004.86  5235.0 1010.67  5358.7 1014.35
  5495.2 1019.81  5508.3 1021.52  5547.0 1023.64  5616.4 1030.32  5628.9 1032.80
  5639.6 1033.24  5650.9 1035.82  5668.2 1036.99  5673.7 1038.76  5705.7 1041.70
#Mann=5,-1,0
  4300.8    0.05       0  4987.7    0.03       0  5020.1    0.05       0
  5104.0    0.12       0  5358.7    0.05       0
Bank Sta=4987.7,5020.1
Exp/Cntr=0.3,0.1

Type RM Length L Ch R = 1,24686,398,398,398
BEGIN DESCRIPTION:
WHITE CREEK 45.0
END DESCRIPTION:
XS GIS Cut Line= 3
      2869122.27     10154021.67      2869556.66     10153660.74
      2869909.74     10153317.20
#Sta/Elev= 30
  4579.2 1013.29  4751.5 1013.86  4793.2 1015.66  4821.8 1014.54  4829.6 1013.41
  4843.7 1013.47  4914.3 1008.54  4921.7 1007.47  4928.6 1005.24  4935.1 1004.90
  4957.2 1001.87  4978.1  996.89  4985.9  995.96  4990.5  992.27  4991.1  989.27
  5022.4  989.27  5022.9  992.27  5064.0  993.58  5077.7  995.29  5084.8  995.19
  5099.2  996.46  5105.7  997.74  5177.0 1004.57  5217.5 1006.48  5254.7 1008.55
  5353.9 1011.87  5389.1 1013.00  5509.3 1019.14  5629.6 1026.61  5636.6 1027.56
#Mann=5,-1,0
  4579.2    0.05       0  4990.5    0.03       0  5022.9    0.05       0
  5217.5    0.12       0  5353.9    0.05       0
Bank Sta=4990.5,5022.9
Exp/Cntr=0.3,0.1

Type RM Length L Ch R = 1,24288,723,723,723
BEGIN DESCRIPTION:
WHITE CREEK 44.0
END DESCRIPTION:
XS GIS Cut Line= 3
      2869540.66     10154222.90      2869882.43     10153826.83
      2870177.93     10153380.77
#Sta/Elev= 30
  4604.9 1017.40  4707.9 1016.08  4792.4 1012.73  4849.4 1008.14  4856.0 1006.39
  4892.2 1002.49  4898.8 1002.45  4920.7  999.29  4927.3  999.13  4934.8  997.18
  4941.6  994.46  4948.2  993.60  4962.4  993.56  4989.0  988.53  4989.5  985.53
  5020.8  985.53  5021.4  988.53  5027.1  990.12  5033.7  990.55  5040.5  992.18
  5068.8  993.38  5083.1  994.88  5128.0 1003.49  5444.4 1020.79  5579.9 1030.16
  5601.0 1032.01  5610.0 1033.84  5616.0 1033.78  5637.1 1036.13  5663.1 1037.35
#Mann=3,-1,0
  4604.9    0.05       0  4989.0    0.05       0  5021.4    0.05       0
Bank Sta=4989,5021.4
Exp/Cntr=0.3,0.1

Type RM Length L Ch R = 1,23565,409,409,409
BEGIN DESCRIPTION:
WHITE CREEK 43.0
END DESCRIPTION:
XS GIS Cut Line= 3
      2868997.73     10155161.87      2870125.17     10154484.77
      2870772.09     10154162.91
#Sta/Elev= 30
  3516.6 1016.66  3739.6 1009.27  3850.4 1007.98  3893.1 1008.92  3957.5 1006.44
  4009.7 1008.16  4285.7 1009.16  4424.1 1006.77  4540.7 1007.27  4645.2 1004.55
  4709.3 1006.31  4746.2 1004.54  4767.6 1005.69  4825.9 1004.35  4892.7  999.90
  4915.1  997.23  4944.0  987.64  4994.8  985.45  4995.3  982.45  5026.7  982.45
  5027.2  985.45  5033.4  988.53  5071.8  991.39  5100.7  999.02  5122.7 1002.91
  5167.4 1007.25  5334.9 1017.98  5376.4 1021.90  5456.7 1027.56  5554.3 1031.84
#Mann=6,-1,0
  3516.6    0.05       0  4994.8    0.05       0  5027.2    0.05       0
  5100.7    0.12       0  5376.4    0.05       0  5456.7    0.12       0
Bank Sta=4994.8,5027.2
Exp/Cntr=0.3,0.1

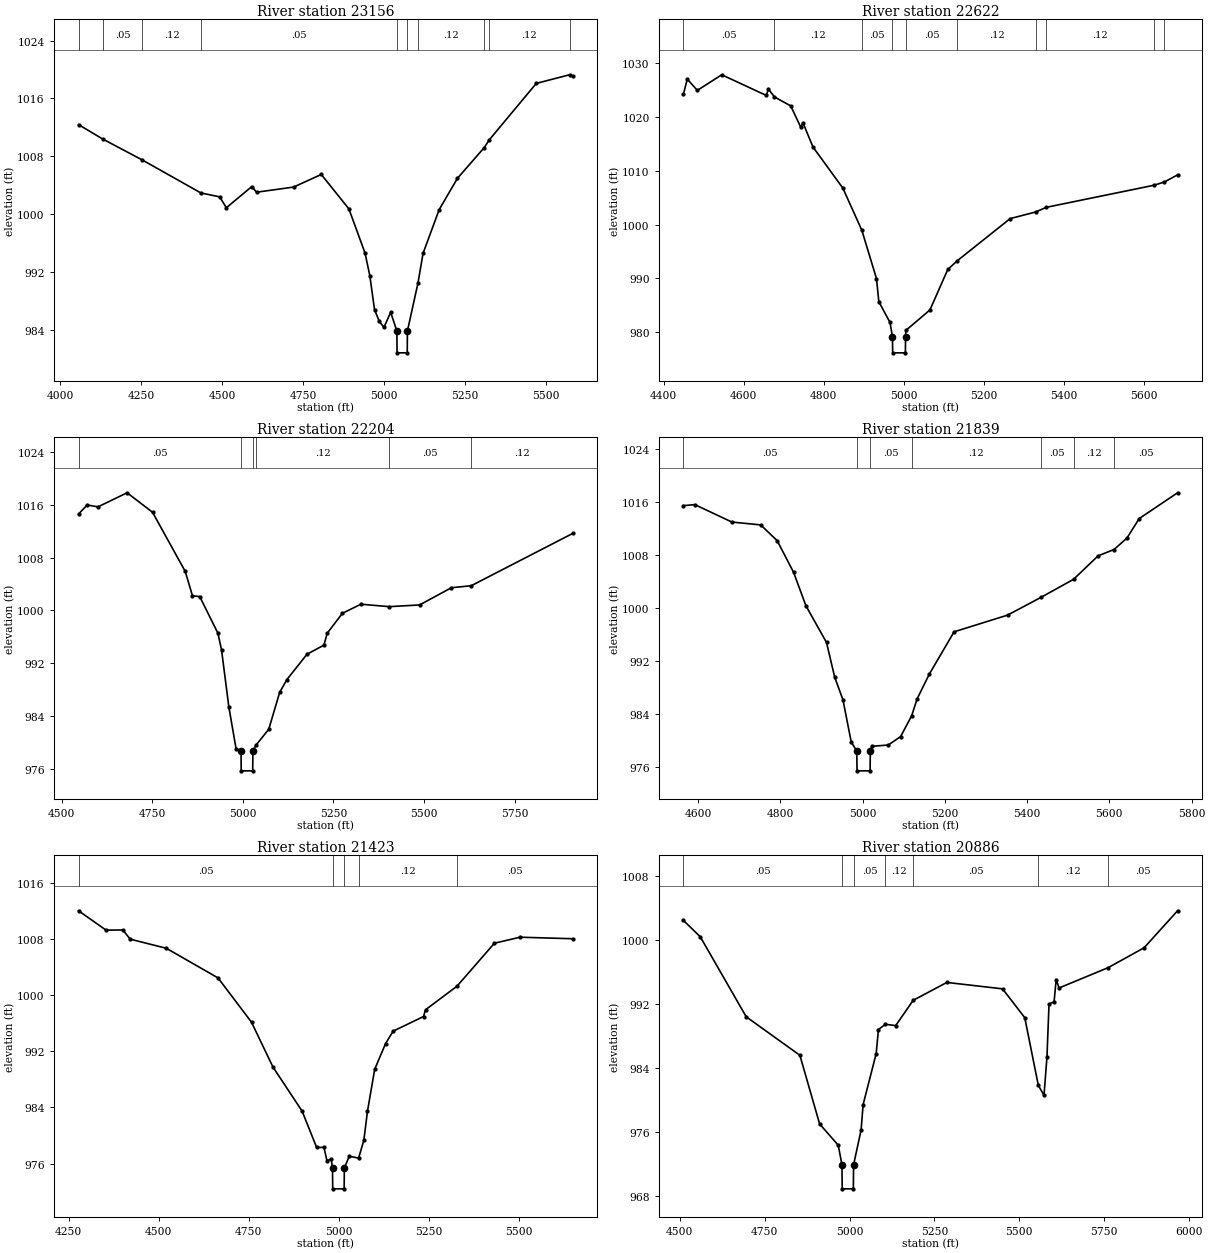
Type RM Length L Ch R = 1,23156,534,534,534
BEGIN DESCRIPTION:
WHITE CREEK 42.0
END DESCRIPTION:
XS GIS Cut Line= 3
      2869722.73     10155442.95      2870035.74     10155062.87
      2870859.77     10154440.06
#Sta/Elev= 30
  4057.5 1012.39  4131.7 1010.41  4254.7 1007.50  4435.1 1002.96  4493.0 1002.42
  4513.8 1000.92  4592.3 1003.84  4606.9 1003.06  4721.3 1003.77  4806.7 1005.51
  4892.0 1000.76  4941.9  994.65  4956.5  991.56  4971.1  986.87  4985.6  985.25
  5000.2  984.40  5021.0  986.49  5040.1  983.89  5040.7  980.89  5072.1  980.89
  5072.6  983.89  5105.4  990.56  5120.9  994.62  5170.8 1000.67  5227.1 1004.98
  5309.8 1009.22  5325.0 1010.27  5470.5 1018.08  5573.0 1019.27  5582.8 1019.13
#Mann=10,-1,0
  4057.5    0.12       0  4131.7    0.05       0  4254.7    0.12       0
  4435.1    0.05       0  5040.1    0.05       0  5072.6    0.05       0
  5105.4    0.12       0  5309.8    0.05       0  5325.0    0.12       0
  5573.0    0.05       0
Bank Sta=5040.1,5072.6
Exp/Cntr=0.3,0.1

Type RM Length L Ch R = 1,22622,418,418,418
BEGIN DESCRIPTION:
WHITE CREEK 41.0
END DESCRIPTION:
XS GIS Cut Line= 3
      2870578.70     10155650.57      2870696.88     10155327.96
      2871089.28     10154527.21
#Sta/Elev= 30
  4449.4 1024.25  4458.9 1027.03  4484.1 1024.94  4545.1 1027.84  4656.5 1024.00
  4661.8 1025.18  4677.0 1023.72  4717.5 1022.06  4742.7 1018.09  4748.1 1018.94
  4773.2 1014.42  4847.8 1006.79  4895.3  998.96  4932.0  989.96  4937.8  985.68
  4965.8  981.81  4971.9  979.17  4972.5  976.17  5004.2  976.17  5004.7  979.17
  5005.3  980.33  5065.6  984.14  5110.2  991.66  5134.4  993.31  5266.1 1001.11
  5330.1 1002.35  5356.6 1003.21  5626.2 1007.32  5651.8 1007.92  5684.7 1009.24
#Mann=10,-1,0
  4449.4    0.05       0  4677.0    0.12       0  4895.3    0.05       0
  4971.9    0.05       0  5004.7    0.05       0  5134.4    0.12       0
  5330.1    0.05       0  5356.6    0.12       0  5626.2    0.05       0
  5651.8    0.12       0
Bank Sta=4971.9,5004.7
Exp/Cntr=0.3,0.1

Type RM Length L Ch R = 1,22204,365,365,365
BEGIN DESCRIPTION:
WHITE CREEK 40.0
END DESCRIPTION:
XS GIS Cut Line= 3
      2871140.84     10155736.77      2871182.36     10155107.58
      2871326.08     10154388.97
#Sta/Elev= 30
  4546.9 1014.60  4570.6 1015.97  4600.7 1015.69  4680.8 1017.82  4751.0 1014.87
  4841.2 1005.91  4861.2 1002.22  4881.3 1002.09  4931.4  996.55  4941.4  994.02
  4961.5  985.41  4981.5  979.05  4995.2  978.70  4995.7  975.70  5027.4  975.70
  5028.0  978.70  5035.7  979.54  5071.7  982.00  5101.8  987.58  5121.8  989.53
  5177.2  993.36  5223.9  994.74  5233.0  996.55  5274.9  999.56  5325.9 1000.94
  5404.2 1000.57  5488.0 1000.83  5575.7 1003.44  5630.4 1003.74  5910.3 1011.66
#Mann=6,-1,0
  4546.9    0.05       0  4995.2    0.05       0  5028.0    0.05       0
  5035.7    0.12       0  5404.2    0.05       0  5630.4    0.12       0
Bank Sta=4995.2,5028
Exp/Cntr=0.3,0.1

Type RM Length L Ch R = 1,21839,416,416,416
BEGIN DESCRIPTION:
Mapping XS 88cea96f
END DESCRIPTION:
XS GIS Cut Line= 2
      2871536.88     10155720.85      2871527.30     10154519.89
#Sta/Elev= 30
  4564.8 1015.46  4592.5 1015.61  4682.5 1012.98  4752.5 1012.55  4792.5 1010.18
  4832.5 1005.39  4862.5 1000.34  4912.5  994.80  4932.5  989.54  4952.5  986.14
  4972.6  979.77  4986.1  978.42  4986.7  975.42  5018.4  975.42  5019.0  978.42
  5022.6  979.12  5062.6  979.32  5092.6  980.59  5119.6  983.75  5132.6  986.27
  5162.6  990.05  5222.6  996.41  5352.6  998.93  5433.2 1001.59  5512.9 1004.33
  5572.6 1007.88  5611.2 1008.83  5642.6 1010.55  5672.6 1013.51  5765.8 1017.40
#Mann=7,-1,0
  4564.8    0.05       0  4986.1    0.05       0  5019.0    0.05       0
  5119.6    0.12       0  5433.2    0.05       0  5512.9    0.12       0
  5611.2    0.05       0
Bank Sta=4986.1,5019
Exp/Cntr=0.3,0.1

Type RM Length L Ch R = 1,21423,537,537,537
BEGIN DESCRIPTION:
WHITE CREEK 39.0
END DESCRIPTION:
XS GIS Cut Line= 3
      2871827.53     10155874.07      2871931.64     10155287.02
      2871843.58     10154517.45
#Sta/Elev= 30
  4277.6 1012.07  4353.8 1009.31  4400.5 1009.33  4420.8 1008.02  4521.0 1006.72
  4664.5 1002.49  4757.4  996.17  4816.8  989.78  4897.9  983.47  4938.1  978.29
  4958.3  978.31  4966.7  976.41  4978.4  976.63  4982.1  975.39  4982.7  972.39
  5014.4  972.39  5015.0  975.39  5028.7  977.04  5054.5  976.78  5069.0  979.30
  5079.1  983.46  5099.2  989.46  5129.4  993.13  5150.3  994.89  5234.6  996.98
  5240.1  997.94  5327.5 1001.31  5431.3 1007.44  5502.4 1008.30  5648.4 1008.08
#Mann=5,-1,0
  4277.6    0.05       0  4982.1    0.05       0  5015.0    0.05       0
  5054.5    0.12       0  5327.5    0.05       0
Bank Sta=4982.1,5015
Exp/Cntr=0.3,0.1

Type RM Length L Ch R = 1,20886,537,537,537
BEGIN DESCRIPTION:
WHITE CREEK 38.0
END DESCRIPTION:
XS GIS Cut Line= 3
      2872229.96     10155644.15      2872562.12     10154957.47
      2872958.19     10154388.92
#Sta/Elev= 30
  4510.8 1002.41  4560.2 1000.38  4695.7  990.38  4853.8  985.57  4911.9  977.00
  4966.8  974.34  4977.8  971.89  4978.5  968.89  5011.3  968.89  5012.0  971.89
  5034.1  976.23  5040.1  979.41  5078.5  985.77  5085.3  988.79  5105.6  989.44
  5136.0  989.28  5187.7  992.44  5286.8  994.67  5450.8  993.87  5516.3  990.27
  5556.3  981.81  5573.0  980.57  5581.7  985.35  5587.8  991.98  5602.7  992.24
  5608.8  995.02  5617.5  993.98  5762.2  996.52  5867.9  999.00  5966.5 1003.62
#Mann=7,-1,0
  4510.8    0.05       0  4977.8    0.05       0  5012.0    0.05       0
  5105.6    0.12       0  5187.7    0.05       0  5556.3    0.12       0
  5762.2    0.05       0
Bank Sta=4977.8,5012
Exp/Cntr=0.3,0.1

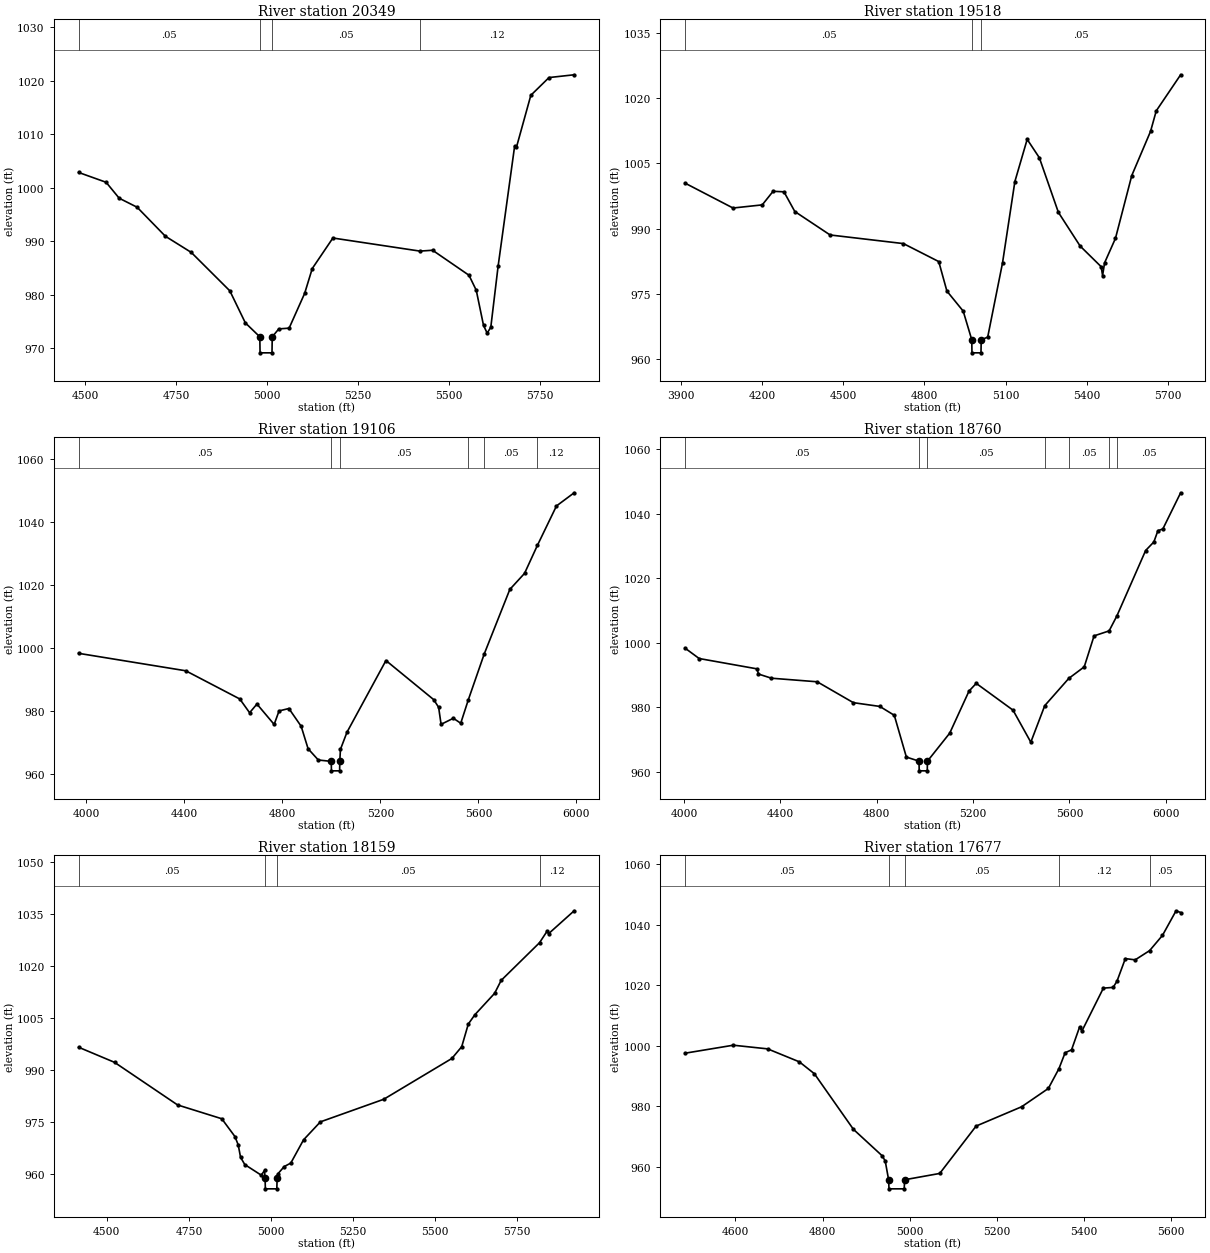
Type RM Length L Ch R = 1,20349,831,831,831
BEGIN DESCRIPTION:
WHITE CREEK 37.0
END DESCRIPTION:
XS GIS Cut Line= 3
      2872469.48     10155874.14      2873022.05     10155382.26
      2873644.87     10155363.10
#Sta/Elev= 30
  4481.7 1002.87  4557.3 1001.03  4593.2  998.05  4642.6  996.36  4720.3  990.93
  4791.4  987.91  4897.6  980.71  4940.2  974.72  4980.0  972.11  4980.7  969.11
  5013.5  969.11  5014.2  972.11  5032.2  973.59  5060.6  973.73  5103.3  980.23
  5124.2  984.88  5181.0  990.60  5420.4  988.15  5455.2  988.31  5555.3  983.63
  5575.3  980.82  5595.3  974.24  5605.3  972.80  5615.3  973.90  5635.3  985.27
  5680.9 1007.83  5685.9 1007.60  5725.4 1017.31  5775.4 1020.63  5844.6 1021.15
#Mann=4,-1,0
  4481.7    0.05       0  4980.0    0.05       0  5014.2    0.05       0
  5420.4    0.12       0
Bank Sta=4980,5014.2
Exp/Cntr=0.3,0.1

Type RM Length L Ch R = 1,19518,412,412,412
BEGIN DESCRIPTION:
WHITE CREEK 36.0
END DESCRIPTION:
XS GIS Cut Line= 3
      2872191.62     10156091.31      2873050.79     10156174.35
      2874015.38     10156279.75
#Sta/Elev= 30
  3914.5 1000.44  4091.8  994.73  4199.9  995.45  4240.1  998.57  4280.3  998.45
  4320.4  993.93  4451.0  988.54  4722.3  986.56  4853.0  982.43  4883.2  975.65
  4943.5  971.05  4975.2  964.47  4975.9  961.47  5009.3  961.47  5010.1  964.47
  5034.1  965.08  5088.9  982.10  5134.7 1000.82  5180.2 1010.50  5225.2 1006.28
  5295.6  993.74  5376.1  986.00  5454.1  981.24  5459.2  979.20  5466.6  982.14
  5506.9  987.77  5567.2 1002.19  5636.7 1012.34  5657.8 1017.05  5748.0 1025.33
#Mann=3,-1,0
  3914.5    0.05       0  4975.2    0.05       0  5010.1    0.05       0
Bank Sta=4975.2,5010.1
Exp/Cntr=0.3,0.1

Type RM Length L Ch R = 1,19106,346,346,346
BEGIN DESCRIPTION:
WHITE CREEK 35.0
END DESCRIPTION:
XS GIS Cut Line= 3
      2872169.31     10156538.46      2873424.48     10156618.30
      2874187.78     10156570.40
#Sta/Elev= 30
  3968.3  998.32  4405.6  992.79  4626.0  983.86  4666.1  979.50  4696.1  982.25
  4766.3  975.79  4786.3  980.07  4826.4  980.84  4876.5  975.22  4904.8  968.09
  4946.6  964.52  4999.3  964.09  5000.1  961.09  5033.5  961.09  5034.2  964.09
  5036.8  967.88  5063.7  973.35  5222.6  996.04  5417.6  983.64  5437.6  981.22
  5447.6  975.82  5497.7  977.75  5527.8  976.17  5558.7  983.58  5623.8  998.14
  5728.2 1018.57  5788.3 1023.66  5840.6 1032.51  5918.6 1045.02  5990.8 1049.19
#Mann=6,-1,0
  3968.3    0.05       0  4999.3    0.05       0  5034.2    0.05       0
  5558.7    0.12       0  5623.8    0.05       0  5840.6    0.12       0
Bank Sta=4999.3,5034.2
Exp/Cntr=0.3,0.1

Type RM Length L Ch R = 1,18760,601,601,601
BEGIN DESCRIPTION:
WHITE CREEK 34.0
END DESCRIPTION:
XS GIS Cut Line= 3
      2872137.33     10156921.72      2873360.60     10156947.28
      2874178.19     10157110.16
#Sta/Elev= 30
  4004.3  998.29  4062.7  995.08  4302.7  991.88  4308.9  990.27  4362.7  988.98
  4552.8  987.87  4702.8  981.40  4812.8  980.23  4872.8  977.48  4922.9  964.54
  4975.4  963.27  4976.1  960.27  5009.6  960.27  5010.4  963.27  5102.9  971.95
  5182.9  984.98  5212.9  987.38  5365.6  979.08  5439.5  969.15  5497.4  980.48
  5597.2  988.92  5661.3  992.50  5702.1 1002.10  5764.5 1003.64  5796.8 1008.28
  5916.2 1028.56  5950.3 1031.21  5967.2 1034.71  5987.6 1035.23  6061.5 1046.45
#Mann=7,-1,0
  4004.3    0.05       0  4975.4    0.05       0  5010.4    0.05       0
  5497.4    0.12       0  5597.2    0.05       0  5764.5    0.12       0
  5796.8    0.05       0
Bank Sta=4975.4,5010.4
Exp/Cntr=0.3,0.1

Type RM Length L Ch R = 1,18159,482,482,482
BEGIN DESCRIPTION:
WHITE CREEK 33.0
END DESCRIPTION:
XS GIS Cut Line= 3
      2872530.16     10157563.70      2873456.42     10157515.79
      2874037.74     10157483.85
#Sta/Elev= 30
  4414.1  996.61  4523.5  992.25  4715.5  979.95  4850.2  975.96  4890.3  970.82
  4900.3  968.41  4907.4  964.84  4920.3  962.73  4970.4  959.67  4980.4  961.02
  4982.1  958.72  4983.0  955.72  5017.9  955.72  5018.8  958.72  5020.4  959.98
  5040.5  962.16  5060.5  963.16  5099.3  969.87  5150.6  975.06  5343.7  981.59
  5551.2  993.37  5581.2  996.77  5601.3 1003.32  5621.3 1006.00  5681.4 1012.18
  5701.4 1015.92  5818.3 1026.80  5841.4 1030.14  5846.4 1029.45  5923.8 1036.02
#Mann=4,-1,0
  4414.1    0.05       0  4982.1    0.05       0  5018.8    0.05       0
  5818.3    0.12       0
Bank Sta=4982.1,5018.8
Exp/Cntr=0.3,0.1

Type RM Length L Ch R = 1,17677,194,194,194
BEGIN DESCRIPTION:
WHITE CREEK 32.0
END DESCRIPTION:
XS GIS Cut Line= 3
      2872855.70     10157953.11      2873149.80     10157991.68
      2873955.70     10157753.11
#Sta/Elev= 30
  4484.5  997.53  4595.1 1000.17  4673.9  998.96  4746.7  994.67  4781.1  990.75
  4870.7  972.37  4936.6  963.63  4943.7  961.91  4951.5  955.69  4952.4  952.69
  4987.3  952.69  4988.2  955.69  5068.8  957.78  5152.3  973.44  5256.7  979.82
  5318.0  985.87  5342.3  992.40  5356.5  997.67  5371.3  998.65  5389.8 1006.22
  5395.0 1004.84  5444.3 1019.04  5466.7 1019.28  5475.6 1021.35  5494.7 1028.80
  5517.3 1028.39  5550.4 1031.44  5579.9 1036.47  5611.1 1044.61  5621.6 1044.04
#Mann=5,-1,0
  4484.5    0.05       0  4951.5    0.05       0  4988.2    0.05       0
  5342.3    0.12       0  5550.4    0.05       0
Bank Sta=4951.5,4988.2
Exp/Cntr=0.3,0.1

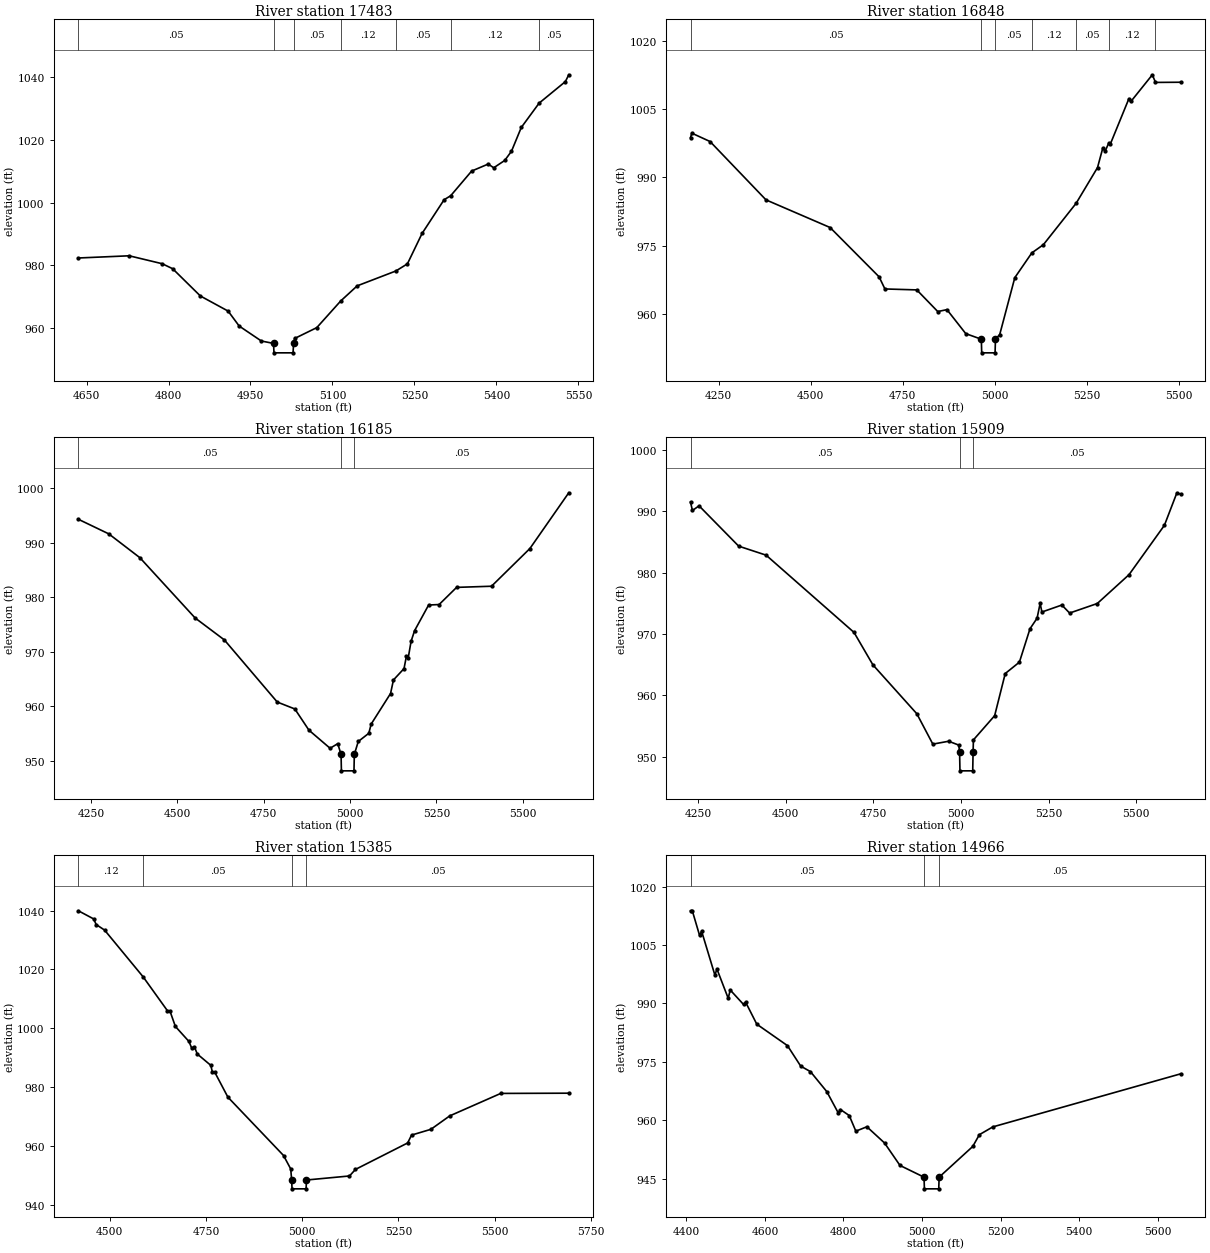
Type RM Length L Ch R = 1,17483,635,635,635
BEGIN DESCRIPTION:
WHITE CREEK 31.0
END DESCRIPTION:
XS GIS Cut Line= 3
      2873105.64     10158153.12      2873699.16     10158052.37
      2873991.87     10158014.19
#Sta/Elev= 30
  4635.1  982.37  4728.1  983.07  4788.4  980.55  4807.6  978.96  4858.3  970.29
  4909.1  965.48  4929.3  960.73  4969.9  955.97  4992.1  955.21  4993.0  952.21
  5027.9  952.21  5028.8  955.21  5030.7  956.77  5071.3  960.23  5115.1  968.71
  5145.2  973.51  5216.0  978.24  5237.1  980.51  5263.9  990.17  5304.2 1000.89
  5316.3 1002.17  5354.6 1010.01  5384.9 1012.24  5395.0 1011.06  5415.1 1013.38
  5427.5 1016.31  5445.4 1023.87  5478.1 1031.62  5526.1 1038.46  5532.3 1040.63
#Mann=7,-1,0
  4635.1    0.05       0  4992.1    0.05       0  5028.8    0.05       0
  5115.1    0.12       0  5216.0    0.05       0  5316.3    0.12       0
  5478.1    0.05       0
Bank Sta=4992.1,5028.8
Exp/Cntr=0.3,0.1

Type RM Length L Ch R = 1,16848,663,663,663
BEGIN DESCRIPTION:
WHITE CREEK 30.0
END DESCRIPTION:
XS GIS Cut Line= 3
      2872945.37     10158828.49      2873916.34     10158620.88
      2874141.93     10158369.88
#Sta/Elev= 30
  4174.0  998.77  4177.6  999.74  4227.1  997.90  4378.8  985.07  4552.7  978.99
  4685.6  968.15  4701.4  965.48  4787.9  965.27  4844.8  960.51  4869.7  960.93
  4920.8  955.65  4963.0  954.43  4964.0  951.43  5000.3  951.43  5001.3  954.43
  5012.9  955.46  5053.8  967.96  5100.0  973.41  5131.4  975.22  5220.2  984.32
  5278.2  992.17  5292.4  996.44  5299.1  995.81  5308.2  997.49  5313.3  997.41
  5363.4 1007.34  5370.1 1006.84  5426.9 1012.58  5435.5 1010.90  5504.4 1010.94
#Mann=7,-1,0
  4174.0    0.05       0  4963.0    0.03       0  5001.3    0.05       0
  5100.0    0.12       0  5220.2    0.05       0  5308.2    0.12       0
  5435.5    0.05       0
Bank Sta=4963,5001.3
Exp/Cntr=0.3,0.1

Type RM Length L Ch R = 1,16185,276,276,276
BEGIN DESCRIPTION:
WHITE CREEK 29.0
END DESCRIPTION:
XS GIS Cut Line= 3
      2872891.07     10159141.49      2873865.24     10159336.32
      2874286.87     10159400.20
#Sta/Elev= 30
  4213.4  994.25  4301.5  991.58  4391.5  987.22  4551.3  976.20  4636.2  972.17
  4789.2  960.81  4840.2  959.54  4881.0  955.66  4942.2  952.35  4964.4  953.19
  4974.0  951.22  4975.0  948.22  5011.4  948.22  5012.4  951.22  5023.8  953.59
  5054.3  955.09  5061.2  956.78  5117.3  962.37  5125.7  964.85  5156.3  966.93
  5163.2  969.19  5168.3  968.83  5176.7  971.91  5186.9  973.87  5227.5  978.56
  5257.9  978.65  5308.5  981.79  5409.6  982.00  5520.8  988.90  5633.3  999.10
#Mann=3,-1,0
  4213.4    0.05       0  4974.0    0.05       0  5012.4    0.05       0
Bank Sta=4974,5012.4
Exp/Cntr=0.3,0.1

Type RM Length L Ch R = 1,15909,524,524,524
BEGIN DESCRIPTION:
WHITE CREEK 28.0
END DESCRIPTION:
XS GIS Cut Line= 3
      2872852.81     10159317.17      2873395.73     10159534.34
      2874202.25     10159639.54
#Sta/Elev= 30
  4229.0  991.51  4234.5  990.15  4253.4  990.91  4366.4  984.33  4444.5  982.86
  4695.2  970.25  4749.1  964.95  4874.2  956.98  4919.9  952.02  4965.0  952.49
  4993.9  951.86  4996.2  950.66  4997.2  947.66  5033.6  947.66  5034.6  950.66
  5035.6  952.71  5096.1  956.66  5126.3  963.54  5166.7  965.40  5196.9  970.85
  5217.1  972.57  5225.8  975.00  5230.8  973.58  5287.7  974.72  5309.8  973.41
  5388.8  974.97  5479.3  979.68  5580.1  987.73  5615.7  993.04  5627.1  992.79
#Mann=3,-1,0
  4229.0    0.05       0  4996.2    0.05       0  5034.6    0.05       0
Bank Sta=4996.2,5034.6
Exp/Cntr=0.3,0.1

Type RM Length L Ch R = 1,15385,419,419,419
BEGIN DESCRIPTION:
WHITE CREEK 27.0
END DESCRIPTION:
XS GIS Cut Line= 3
      2873002.85     10160336.04      2873264.78     10160102.86
      2874181.11     10159991.11
#Sta/Elev= 30
  4418.8 1039.91  4458.4 1037.15  4465.1 1035.23  4486.9 1033.35  4587.1 1017.46
  4649.9 1006.01  4656.6 1005.89  4670.8 1000.63  4705.9  995.55  4713.5  993.18
  4720.2  993.70  4727.7  991.27  4762.8  987.42  4766.7  985.23  4772.5  985.23
  4807.2  976.62  4951.7  956.81  4970.4  952.24  4972.8  948.49  4973.8  945.49
  5010.3  945.49  5011.3  948.49  5123.0  949.86  5138.6  952.09  5274.1  961.07
  5284.2  963.74  5334.5  965.70  5383.4  970.26  5515.9  977.89  5692.6  977.97
#Mann=4,-1,0
  4418.8    0.12       0  4587.1    0.05       0  4972.8    0.03       0
  5011.3    0.05       0
Bank Sta=4972.8,5011.3
Exp/Cntr=0.3,0.1

Type RM Length L Ch R = 1,14966,668,668,668
BEGIN DESCRIPTION:
WHITE CREEK 26.0
END DESCRIPTION:
XS GIS Cut Line= 3
      2873101.87     10160655.41      2873444.55     10160557.72
      2874245.36     10160163.52
#Sta/Elev= 30
  4410.5 1013.81  4415.1 1013.81  4433.6 1007.48  4438.8 1008.55  4472.6  997.29
  4477.8  998.84  4506.5  991.33  4511.7  993.45  4545.5  989.74  4550.7  990.36
  4579.3  984.67  4657.4  979.16  4691.2  973.89  4716.0  972.48  4757.6  967.34
  4786.7  961.88  4792.3  962.74  4814.7  961.20  4831.6  957.18  4859.7  958.31
  4904.6  954.15  4944.0  948.37  5005.2  945.36  5006.2  942.36  5042.7  942.36
  5043.7  945.36  5129.3  953.25  5146.2  956.28  5180.5  958.28  5659.4  971.93
#Mann=3,-1,0
  4410.5    0.05       0  5005.2    0.05       0  5043.7    0.05       0
Bank Sta=5005.2,5043.7
Exp/Cntr=0.3,0.1