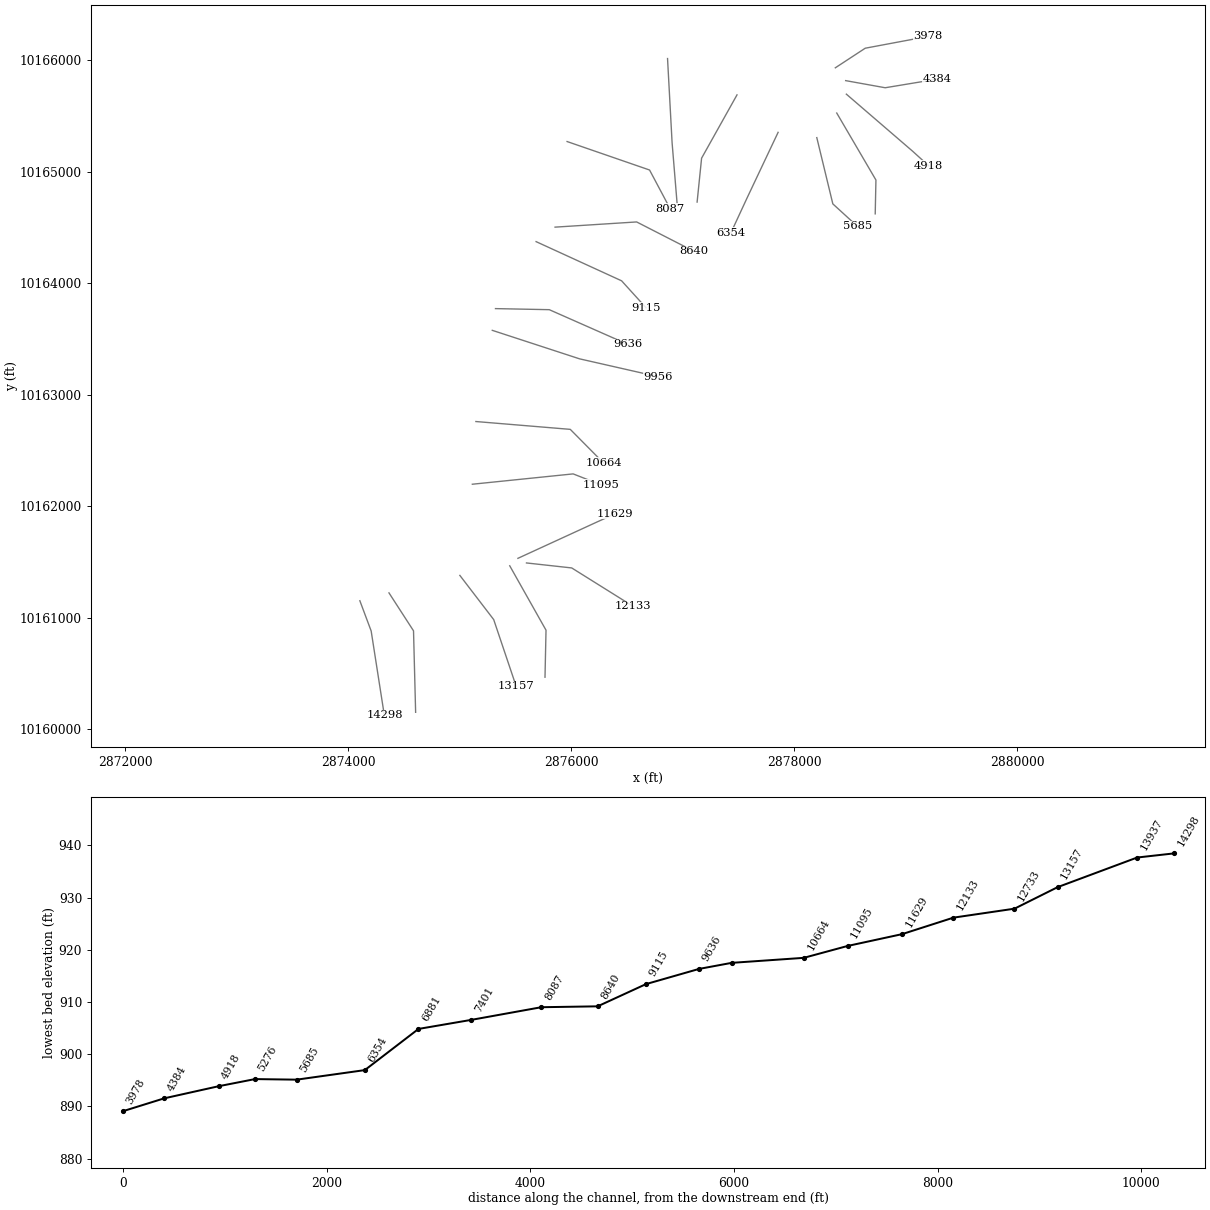
HEC-RAS study WHITE CREEK.prj: WHITE CREEK Base Level Engineering

--- WHITE CREEK.g01 (geometry) --- (continued)

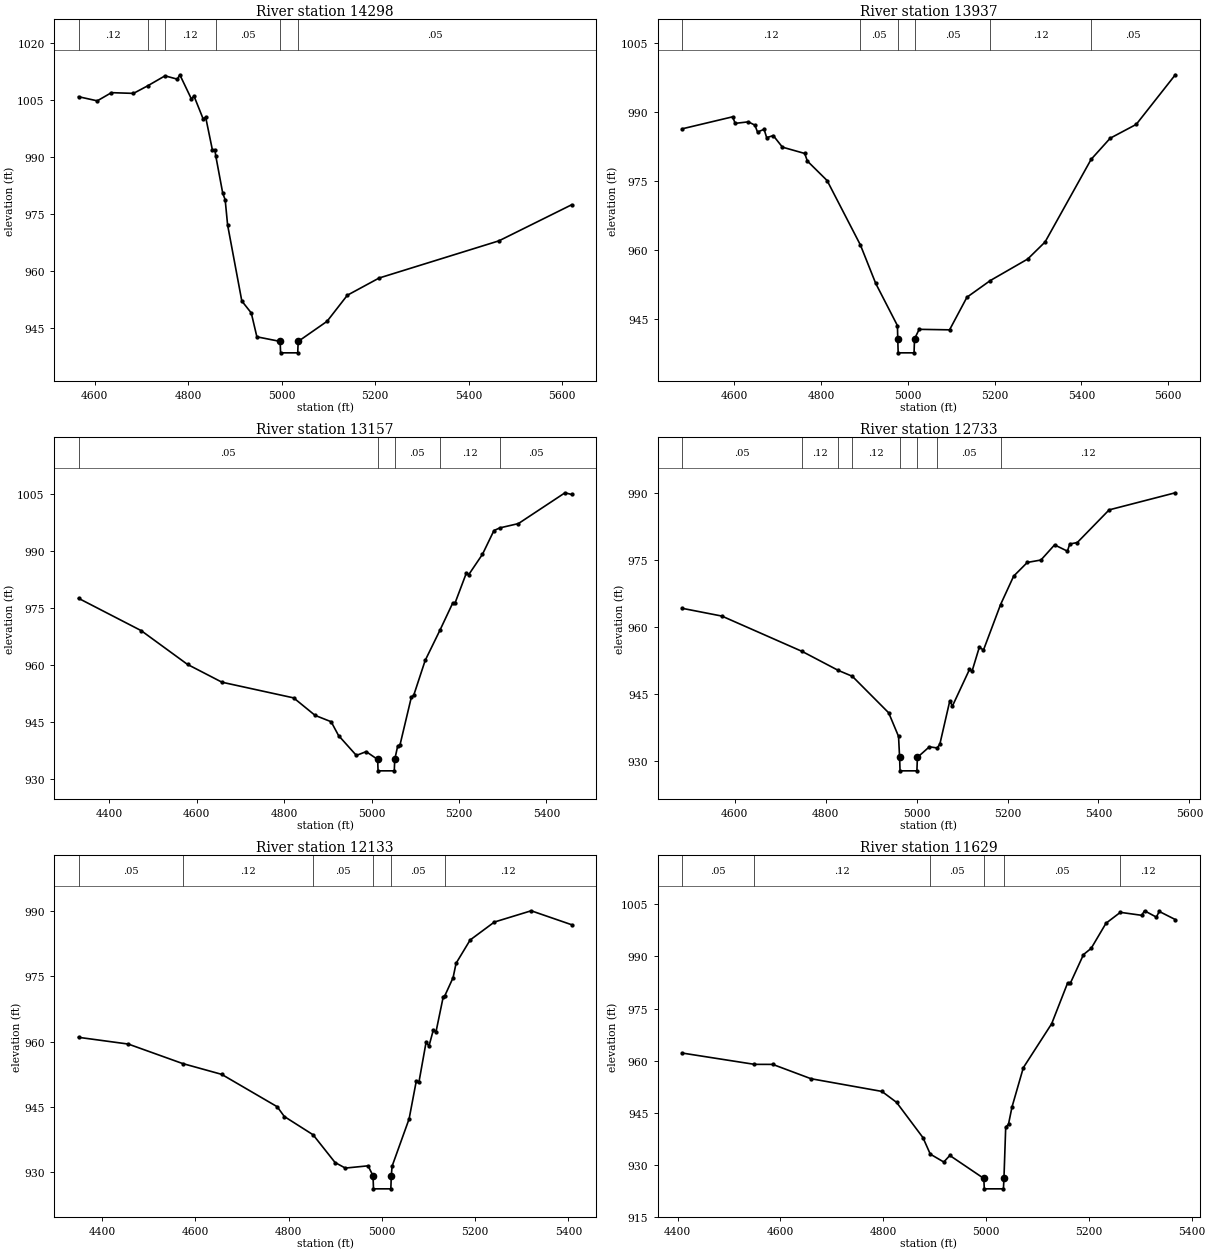
Type RM Length L Ch R = 1,14298,361,361,361
BEGIN DESCRIPTION:
WHITE CREEK 25.0
END DESCRIPTION:
XS GIS Cut Line= 3
      2874105.67     10161153.16      2874206.99     10160882.17
      2874324.94     10160126.63
#Sta/Elev= 30
  4565.8 1005.79  4605.9 1004.70  4636.2 1006.85  4683.3 1006.66  4713.7 1008.65
  4750.7 1011.27  4777.0 1010.40  4782.4 1011.55  4807.3 1005.15  4812.6 1005.99
  4832.3  999.93  4837.6 1000.42  4851.9  991.86  4857.2  991.86  4859.3  990.18
  4874.2  980.37  4879.3  978.72  4884.5  972.10  4914.9  952.10  4935.1  948.96
  4947.1  942.69  4996.8  941.48  4997.8  938.48  5034.4  938.48  5035.4  941.48
  5097.1  946.76  5140.5  953.62  5208.4  958.14  5464.5  967.91  5619.8  977.38
#Mann=6,-1,0
  4565.8    0.12       0  4713.7    0.05       0  4750.7    0.12       0
  4859.3    0.05       0  4996.8    0.05       0  5035.4    0.05       0
Bank Sta=4996.8,5035.4
Exp/Cntr=0.3,0.1

Type RM Length L Ch R = 1,13937,780,780,780
BEGIN DESCRIPTION:
WHITE CREEK 24.0
END DESCRIPTION:
XS GIS Cut Line= 3
      2874366.67     10161223.94      2874586.74     10160883.63
      2874605.68     10160153.15
#Sta/Elev= 30
  4480.3  986.29  4596.3  988.89  4602.3  987.47  4632.6  987.80  4647.7  987.08
  4653.7  985.59  4668.9  986.18  4674.8  984.37  4690.0  984.82  4711.1  982.31
  4762.5  980.94  4768.5  979.30  4814.0  975.07  4890.8  961.08  4926.1  952.74
  4976.1  943.59  4976.8  940.69  4977.8  937.69  5014.4  937.69  5015.4  940.69
  5026.1  942.79  5096.2  942.68  5136.2  949.75  5190.2  953.38  5276.2  958.04
  5316.2  961.73  5422.3  979.66  5466.3  984.25  5526.3  987.25  5616.3  998.01
#Mann=6,-1,0
  4480.3    0.12       0  4890.8    0.05       0  4976.8    0.05       0
  5015.4    0.05       0  5190.2    0.12       0  5422.3    0.05       0
Bank Sta=4976.8,5015.4
Exp/Cntr=0.3,0.1

Type RM Length L Ch R = 1,13157,424,424,424
BEGIN DESCRIPTION:
WHITE CREEK 23.0
END DESCRIPTION:
XS GIS Cut Line= 3
      2875002.26     10161380.43      2875305.69     10160984.38
      2875506.73     10160387.66
#Sta/Elev= 30
  4329.1  977.46  4472.5  968.95  4578.6  960.05  4657.5  955.36  4821.6  951.23
  4870.6  946.63  4907.4  944.95  4924.3  941.32  4965.1  936.08  4987.6  937.08
  5013.8  935.02  5014.8  932.02  5051.9  932.02  5052.9  935.02  5059.6  938.49
  5064.9  938.81  5091.1  951.49  5096.3  951.88  5122.6  961.09  5156.6  969.10
  5185.5  976.17  5190.8  976.16  5217.0  984.15  5222.3  983.69  5253.8  989.06
  5280.0  995.30  5293.4  996.00  5335.9  997.13  5442.7 1005.25  5457.7 1004.80
#Mann=5,-1,0
  4329.1    0.05       0  5013.8    0.05       0  5052.9    0.05       0
  5156.6    0.12       0  5293.4    0.05       0
Bank Sta=5013.8,5052.9
Exp/Cntr=0.3,0.1

Type RM Length L Ch R = 1,12733,600,600,600
BEGIN DESCRIPTION:
WHITE CREEK 22.0
END DESCRIPTION:
XS GIS Cut Line= 3
      2875449.40     10161466.69      2875774.75     10160889.41
      2875765.63     10160467.56
#Sta/Elev= 30
  4484.4  964.19  4571.5  962.46  4748.4  954.55  4827.5  950.33  4858.5  949.01
  4938.5  940.85  4960.2  935.58  4962.5  930.89  4963.5  927.89  5000.6  927.89
  5001.6  930.89  5028.0  933.26  5045.1  933.00  5051.0  933.83  5072.9  943.51
  5078.7  942.36  5116.2  950.53  5122.0  950.19  5137.9  955.51  5147.0  954.87
  5184.6  965.03  5213.4  971.38  5243.4  974.44  5273.4  974.98  5303.4  978.36
  5331.7  976.96  5336.7  978.55  5353.4  978.89  5423.4  986.18  5569.0  990.00
#Mann=8,-1,0
  4484.4    0.05       0  4748.4    0.12       0  4827.5    0.05       0
  4858.5    0.12       0  4962.5    0.07       0  5001.6    0.12       0
  5045.1    0.05       0  5184.6    0.12       0
Bank Sta=4962.5,5001.6
Exp/Cntr=0.3,0.1

Type RM Length L Ch R = 1,12133,504,504,504
BEGIN DESCRIPTION:
WHITE CREEK 21.0
END DESCRIPTION:
XS GIS Cut Line= 3
      2875599.57     10161492.21      2876005.16     10161447.49
      2876555.67     10161103.12
#Sta/Elev= 30
  4349.3  960.99  4456.1  959.44  4572.4  954.97  4656.3  952.48  4775.4  945.04
  4790.7  942.79  4852.4  938.59  4899.5  932.22  4921.5  930.94  4970.3  931.46
  4980.9  929.17  4981.9  926.17  5019.1  926.17  5020.1  929.17  5021.8  931.37
  5058.3  942.25  5073.6  950.90  5079.5  950.77  5094.9  959.98  5100.8  958.94
  5110.2  962.66  5116.1  962.32  5131.4  970.26  5135.0  970.57  5152.6  974.70
  5159.0  978.00  5189.2  983.36  5241.1  987.48  5320.1  990.07  5406.7  986.87
#Mann=6,-1,0
  4349.3    0.05       0  4572.4    0.12       0  4852.4    0.05       0
  4980.9    0.05       0  5020.1    0.05       0  5135.0    0.12       0
Bank Sta=4980.9,5020.1
Exp/Cntr=0.3,0.1

Type RM Length L Ch R = 1,11629,534,534,534
BEGIN DESCRIPTION:
WHITE CREEK 20.0
END DESCRIPTION:
XS GIS Cut Line= 3
      2875522.84     10161533.71      2876231.93     10161859.51
      2876394.78     10161932.95
#Sta/Elev= 30
  4409.1  962.16  4549.6  958.90  4585.1  958.89  4659.5  954.76  4797.4  951.10
  4825.9  947.95  4877.3  937.77  4891.5  933.02  4917.8  930.74  4929.5  932.63
  4995.6  926.01  4996.6  923.01  5033.8  923.01  5034.8  926.01  5038.2  940.72
  5043.7  941.70  5050.5  946.63  5072.5  957.94  5127.6  970.61  5158.6  982.35
  5164.1  982.35  5189.5  990.55  5204.5  992.36  5233.3  999.59  5261.2 1002.73
  5302.7 1001.87  5308.2 1003.18  5331.3 1001.35  5336.8 1002.99  5368.1 1000.65
#Mann=6,-1,0
  4409.1    0.05       0  4549.6    0.12       0  4891.5    0.05       0
  4995.6    0.05       0  5034.8    0.05       0  5261.2    0.12       0
Bank Sta=4995.6,5034.8
Exp/Cntr=0.3,0.1

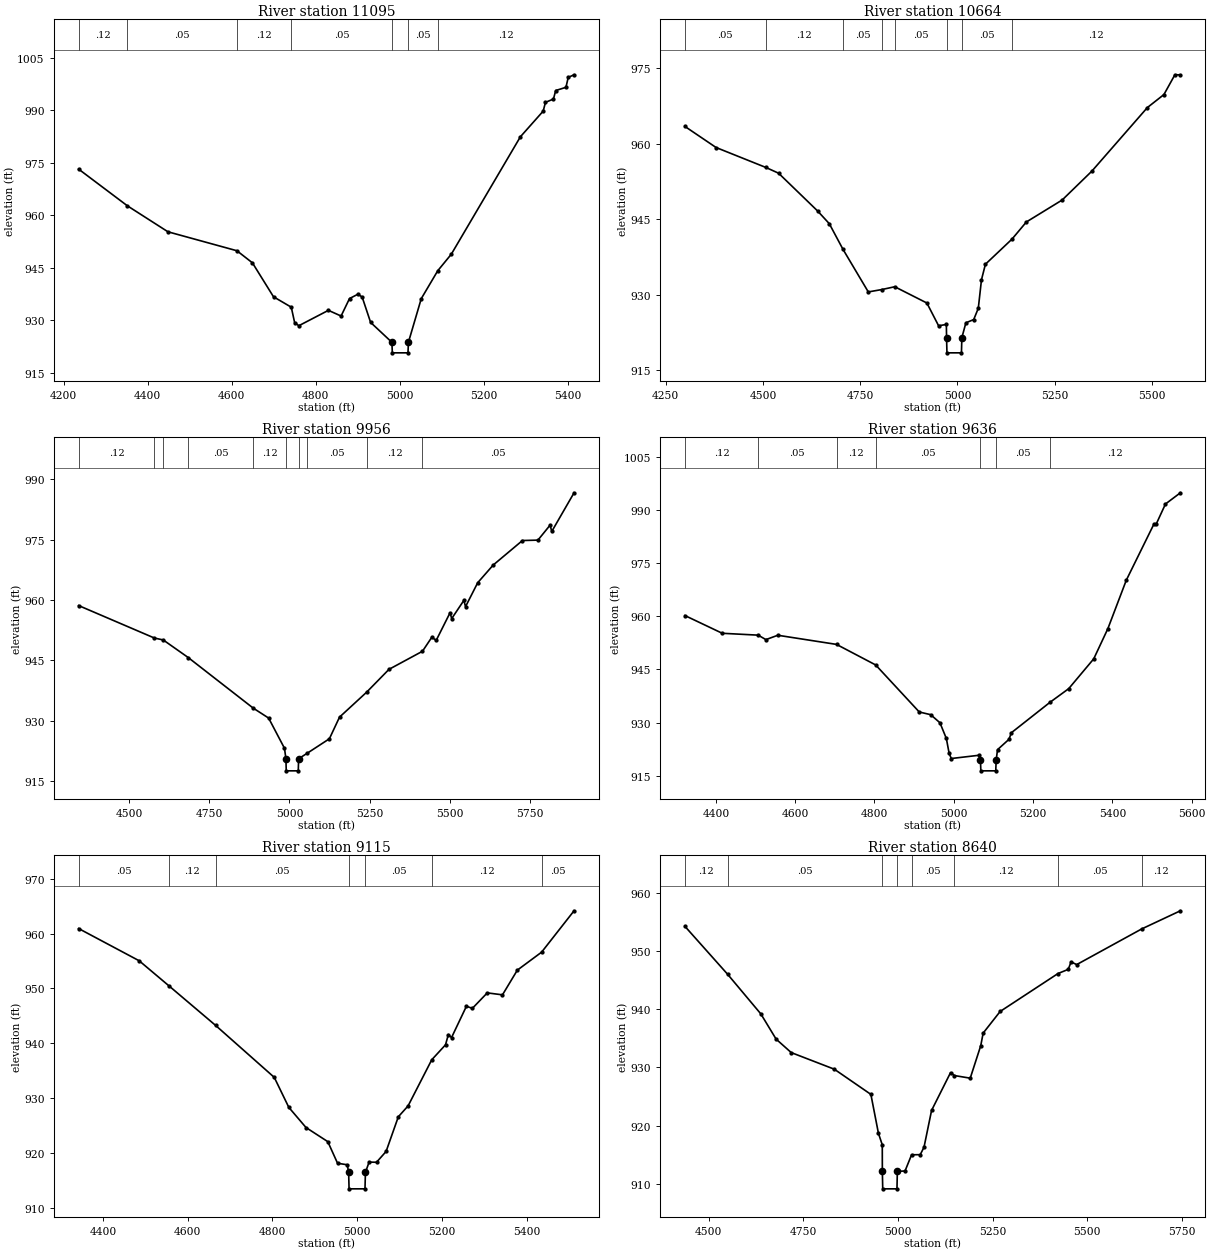
Type RM Length L Ch R = 1,11095,431,431,431
BEGIN DESCRIPTION:
WHITE CREEK 19.0
END DESCRIPTION:
XS GIS Cut Line= 3
      2875114.09     10162198.07      2876017.94     10162290.69
      2876270.22     10162191.69
#Sta/Elev= 30
  4236.0  973.19  4352.3  962.70  4448.7  955.30  4612.9  949.89  4649.8  946.44
  4700.0  936.75  4742.3  933.78  4750.3  929.39  4760.3  928.49  4830.7  932.88
  4860.9  931.26  4881.0  936.25  4901.1  937.49  4911.1  936.67  4931.2  929.44
  4981.9  923.75  4982.9  920.75  5020.2  920.75  5021.2  923.75  5051.8  936.22
  5091.1  944.19  5123.3  948.90  5287.8  982.42  5342.1  989.75  5347.5  992.25
  5366.5  993.19  5371.9  995.63  5396.3  996.54  5401.7  999.38  5415.6 1000.12
#Mann=7,-1,0
  4236.0    0.12       0  4352.3    0.05       0  4612.9    0.12       0
  4742.3    0.05       0  4981.9    0.05       0  5021.2    0.05       0
  5091.1    0.12       0
Bank Sta=4981.9,5021.2
Exp/Cntr=0.3,0.1

Type RM Length L Ch R = 1,10664,708,708,708
BEGIN DESCRIPTION:
WHITE CREEK 18.0
END DESCRIPTION:
XS GIS Cut Line= 3
      2875145.95     10162760.20      2875992.26     10162689.98
      2876290.86     10162388.27
#Sta/Elev= 30
  4299.4  963.44  4379.4  959.26  4507.0  955.31  4540.0  954.16  4640.3  946.66
  4670.4  944.13  4705.8  939.01  4770.7  930.57  4805.2  931.04  4838.7  931.60
  4921.3  928.37  4951.4  923.85  4971.4  924.11  4971.9  921.47  4972.9  918.47
  5010.2  918.47  5011.2  921.47  5021.6  924.44  5041.7  925.08  5053.5  927.32
  5061.7  933.00  5071.8  936.07  5140.1  941.06  5177.1  944.47  5269.1  948.83
  5345.4  954.56  5488.2  967.20  5530.7  969.78  5558.9  973.71  5573.1  973.70
#Mann=8,-1,0
  4299.4    0.05       0  4507.0    0.12       0  4705.8    0.05       0
  4805.2    0.12       0  4838.7    0.05       0  4971.9    0.05       0
  5011.2    0.05       0  5140.1    0.12       0
Bank Sta=4971.9,5011.2
Exp/Cntr=0.3,0.1

Type RM Length L Ch R = 1,9956,320,320,320
BEGIN DESCRIPTION:
WHITE CREEK 17.0
END DESCRIPTION:
XS GIS Cut Line= 3
      2875292.95     10163577.82      2876075.43     10163322.32
      2876778.07     10163162.63
#Sta/Elev= 30
  4343.0  958.60  4579.3  950.52  4606.6  950.05  4684.6  945.67  4886.7  933.12
  4935.0  930.63  4984.4  923.12  4988.9  920.51  4989.9  917.51  5027.4  917.51
  5028.4  920.51  5054.7  921.86  5124.3  925.48  5155.9  930.86  5240.2  937.05
  5310.0  942.74  5414.4  947.24  5443.3  950.70  5457.3  949.97  5500.3  956.81
  5505.5  955.37  5543.4  959.89  5548.5  958.32  5586.5  964.28  5634.7  968.67
  5725.9  974.77  5774.1  974.87  5812.1  978.60  5817.2  977.02  5886.7  986.64
#Mann=10,-1,0
  4343.0    0.12       0  4579.3    0.05       0  4606.6    0.12       0
  4684.6    0.05       0  4886.7    0.12       0  4988.9    0.07       0
  5028.4    0.12       0  5054.7    0.05       0  5240.2    0.12       0
  5414.4    0.05       0
Bank Sta=4988.9,5028.4
Exp/Cntr=0.3,0.1

Type RM Length L Ch R = 1,9636,521,521,521
BEGIN DESCRIPTION:
WHITE CREEK 16.0
END DESCRIPTION:
XS GIS Cut Line= 3
      2875321.67     10163772.66      2875803.94     10163763.08
      2876505.67     10163453.12
#Sta/Elev= 30
  4322.2  960.20  4416.2  955.20  4506.8  954.67  4526.3  953.41  4556.3  954.64
  4704.4  952.06  4803.2  946.25  4913.1  932.97  4941.9  932.21  4965.2  929.93
  4981.4  925.49  4988.5  921.25  4993.9  919.83  5063.9  920.75  5067.4  919.35
  5068.4  916.35  5106.0  916.35  5107.0  919.35  5110.5  922.33  5139.3  925.25
  5145.4  927.11  5243.1  935.73  5290.0  939.56  5353.1  947.98  5388.7  956.49
  5435.3  970.21  5505.3  986.13  5510.7  986.05  5534.0  991.71  5571.7  994.88
#Mann=7,-1,0
  4322.2    0.12       0  4506.8    0.05       0  4704.4    0.12       0
  4803.2    0.05       0  5067.4    0.05       0  5107.0    0.05       0
  5243.1    0.12       0
Bank Sta=5067.4,5107
Exp/Cntr=0.3,0.1

Type RM Length L Ch R = 1,9115,475,475,475
BEGIN DESCRIPTION:
WHITE CREEK 15.0
END DESCRIPTION:
XS GIS Cut Line= 3
      2875685.76     10164373.12      2876452.53     10164021.82
      2876671.72     10163780.12
#Sta/Elev= 30
  4342.4  960.94  4485.3  955.06  4554.9  950.53  4665.7  943.27  4804.3  933.78
  4838.7  928.30  4879.2  924.63  4930.7  922.05  4953.7  918.11  4976.7  917.83
  4979.9  916.44  4980.9  913.44  5018.5  913.44  5019.5  916.44  5028.2  918.32
  5045.7  918.29  5068.3  920.26  5097.2  926.59  5120.2  928.57  5176.1  936.99
  5208.6  939.72  5215.3  941.59  5222.8  941.04  5257.9  946.75  5272.1  946.38
  5307.2  949.20  5343.1  948.84  5378.2  953.35  5435.5  956.63  5512.1  964.18
#Mann=7,-1,0
  4342.4    0.05       0  4554.9    0.12       0  4665.7    0.05       0
  4979.9    0.05       0  5019.5    0.05       0  5176.1    0.12       0
  5435.5    0.05       0
Bank Sta=4979.9,5019.5
Exp/Cntr=0.3,0.1

Type RM Length L Ch R = 1,8640,553,553,553
BEGIN DESCRIPTION:
WHITE CREEK 14.0
END DESCRIPTION:
XS GIS Cut Line= 3
      2875855.68     10164503.11      2876587.25     10164549.74
      2877099.46     10164287.50
#Sta/Elev= 30
  4437.6  954.19  4550.1  945.99  4638.0  939.18  4678.3  934.86  4718.2  932.55
  4832.0  929.70  4928.6  925.38  4948.6  918.69  4958.7  916.73  4958.9  912.18
  4959.9  909.18  4997.5  909.18  4998.5  912.18  5018.8  912.24  5036.1  915.02
  5058.9  915.04  5068.9  916.31  5088.9  922.63  5139.0  929.11  5149.3  928.61
  5191.0  928.16  5218.8  933.74  5225.1  935.89  5270.0  939.60  5422.9  946.11
  5449.8  946.82  5457.4  948.10  5472.2  947.64  5643.7  953.75  5746.1  956.87
#Mann=8,-1,0
  4437.6    0.12       0  4550.1    0.05       0  4958.9    0.07       0
  4998.5    0.05       0  5036.1    0.05       0  5149.3    0.12       0
  5422.9    0.05       0  5643.7    0.12       0
Bank Sta=4958.9,4998.5
Exp/Cntr=0.3,0.1

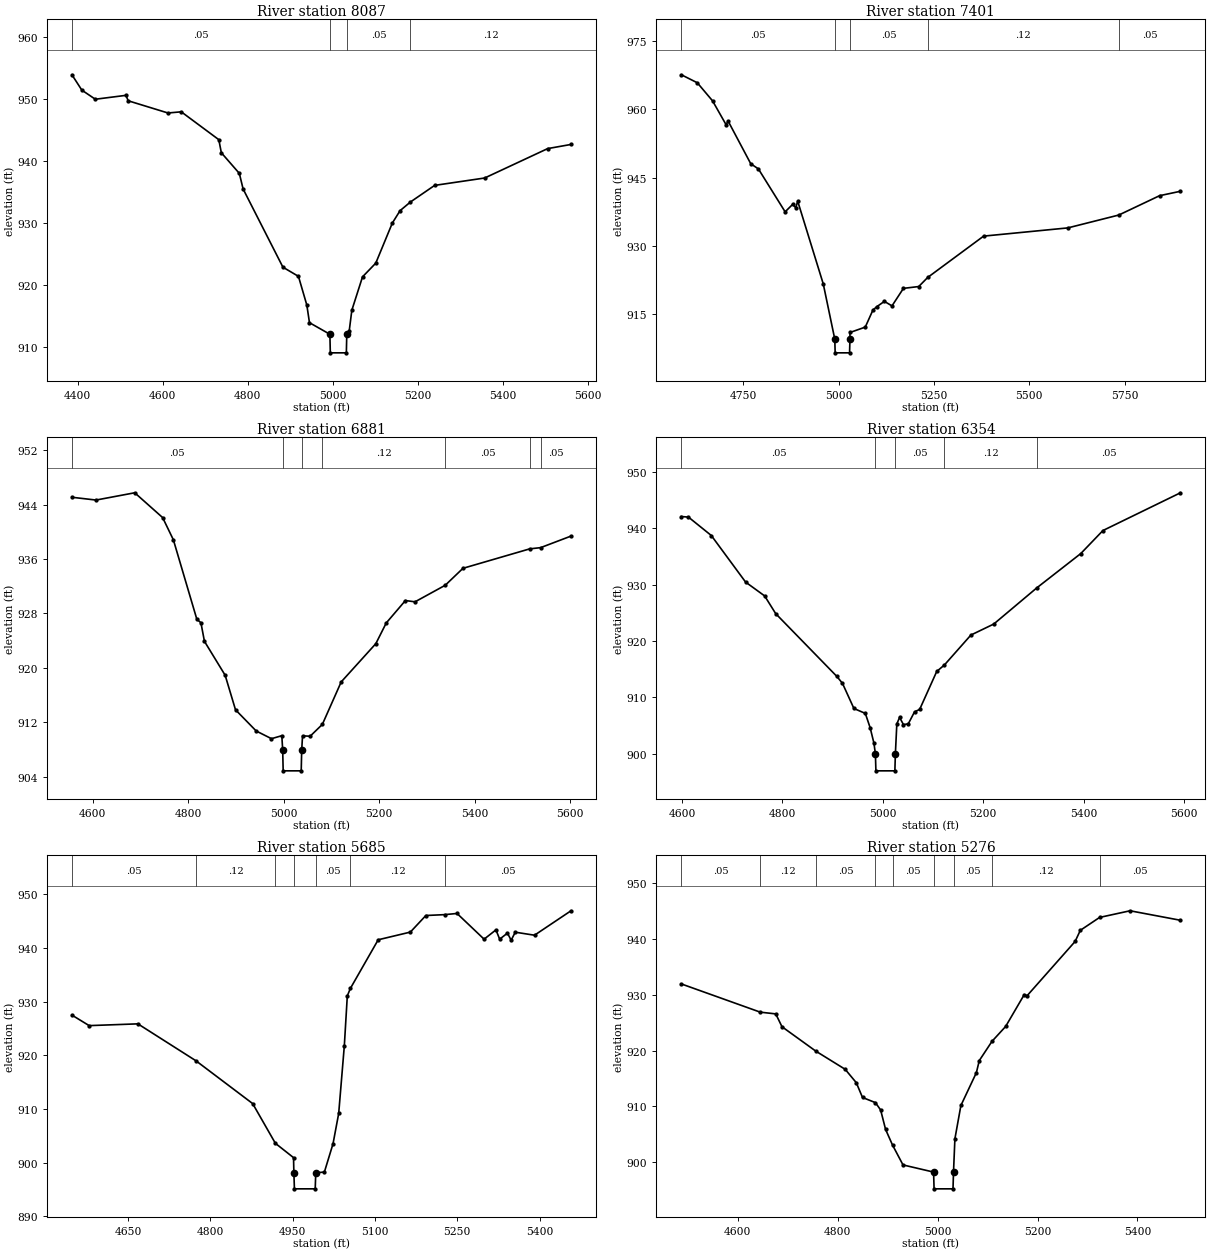
Type RM Length L Ch R = 1,8087,686,686,686
BEGIN DESCRIPTION:
WHITE CREEK 13.0
END DESCRIPTION:
XS GIS Cut Line= 3
      2875963.68     10165270.59      2876703.15     10165015.31
      2876886.67     10164670.16
#Sta/Elev= 30
  4386.4  953.91  4409.7  951.43  4441.4  949.96  4513.4  950.59  4518.7  949.71
  4612.2  947.74  4643.4  947.93  4731.7  943.43  4737.6  941.32  4779.9  937.99
  4788.8  935.47  4882.4  922.84  4918.9  921.36  4938.6  916.72  4944.8  913.88
  4992.8  912.01  4993.8  909.01  5031.5  909.01  5032.5  912.01  5038.3  912.58
  5044.4  915.89  5069.5  921.28  5100.7  923.50  5139.6  929.97  5157.8  931.97
  5182.2  933.37  5239.1  936.05  5356.6  937.24  5504.8  941.99  5559.6  942.66
#Mann=4,-1,0
  4386.4    0.05       0  4992.8    0.05       0  5032.5    0.05       0
  5182.2    0.12       0
Bank Sta=4992.8,5032.5
Exp/Cntr=0.3,0.1

Type RM Length L Ch R = 1,7401,520,520,520
BEGIN DESCRIPTION:
WHITE CREEK 12.0
END DESCRIPTION:
XS GIS Cut Line= 3
      2876864.32     10166014.80      2876905.14     10165259.88
      2876950.56     10164708.47
#Sta/Elev= 30
  4587.2  967.53  4628.9  965.78  4669.0  961.81  4704.6  956.56  4709.6  957.41
  4769.2  948.03  4789.2  946.90  4859.3  937.50  4879.3  939.14  4887.3  938.38
  4892.3  939.84  4959.4  921.69  4989.6  909.59  4990.6  906.59  5028.4  906.59
  5029.4  909.59  5029.5  911.05  5069.6  912.23  5089.6  915.96  5099.6  916.69
  5119.7  917.87  5139.7  916.88  5169.7  920.72  5209.8  921.12  5233.5  923.12
  5380.1  932.17  5600.9  933.97  5734.7  936.79  5841.7  941.03  5896.5  942.00
#Mann=5,-1,0
  4587.2    0.05       0  4989.6    0.05       0  5029.4    0.05       0
  5233.5    0.12       0  5734.7    0.05       0
Bank Sta=4989.6,5029.4
Exp/Cntr=0.3,0.1

Type RM Length L Ch R = 1,6881,527,527,527
BEGIN DESCRIPTION:
WHITE CREEK 11.0
END DESCRIPTION:
XS GIS Cut Line= 3
      2877487.12     10165688.98      2877169.65     10165121.46
      2877129.44     10164727.88
#Sta/Elev= 30
  4556.3  945.09  4606.8  944.68  4687.9  945.75  4746.4  942.10  4768.9  938.83
  4818.1  927.14  4826.6  926.64  4834.0  923.90  4877.4  918.91  4899.1  913.83
  4942.5  910.71  4974.5  909.58  4996.2  910.02  4998.0  907.85  4999.0  904.85
  5036.8  904.85  5037.8  907.85  5039.6  910.00  5055.5  909.94  5081.1  911.68
  5120.6  917.93  5193.2  923.56  5215.0  926.60  5255.2  929.90  5275.3  929.71
  5338.7  932.15  5375.8  934.64  5515.7  937.50  5538.5  937.68  5602.2  939.38
#Mann=7,-1,0
  4556.3    0.05       0  4998.0    0.05       0  5037.8    0.05       0
  5081.1    0.12       0  5338.7    0.05       0  5515.7    0.12       0
  5538.5    0.05       0
Bank Sta=4998,5037.8
Exp/Cntr=0.3,0.1

Type RM Length L Ch R = 1,6354,669,669,669
BEGIN DESCRIPTION:
WHITE CREEK 10.0
END DESCRIPTION:
XS GIS Cut Line= 3
      2877855.67     10165353.07      2877579.01     10164768.12
      2877432.83     10164452.95
#Sta/Elev= 30
  4598.7  942.08  4612.8  941.97  4658.3  938.71  4726.6  930.45  4764.6  927.99
  4786.7  924.84  4908.4  913.72  4919.7  912.48  4942.5  908.02  4965.2  907.15
  4974.8  904.62  4982.4  901.87  4985.3  899.96  4986.3  896.96  5024.1  896.96
  5025.1  899.96  5028.0  905.29  5033.5  906.44  5041.1  905.18  5050.7  905.28
  5063.3  907.43  5073.5  907.86  5107.5  914.59  5122.8  915.74  5175.6  921.05
  5221.1  923.00  5306.9  929.42  5394.6  935.51  5438.7  939.59  5593.2  946.29
#Mann=5,-1,0
  4598.7    0.05       0  4985.3    0.05       0  5025.1    0.05       0
  5122.8    0.12       0  5306.9    0.05       0
Bank Sta=4985.3,5025.1
Exp/Cntr=0.3,0.1

Type RM Length L Ch R = 1,5685,409,409,409
BEGIN DESCRIPTION:
WHITE CREEK 9.0
END DESCRIPTION:
XS GIS Cut Line= 3
      2878202.58     10165305.69      2878346.30     10164711.67
      2878566.69     10164510.44
#Sta/Elev= 30
  4547.8  927.49  4579.2  925.53  4668.0  925.86  4773.7  918.99  4877.2  911.01
  4918.6  903.61  4951.7  900.94  4952.3  898.13  4953.3  895.13  4991.2  895.13
  4992.2  898.13  5007.9  898.25  5023.7  903.54  5034.0  909.17  5044.3  921.82
  5049.7  931.07  5055.3  932.46  5106.0  941.52  5164.6  942.95  5192.9  946.04
  5227.0  946.20  5249.7  946.42  5299.0  941.63  5320.6  943.36  5327.4  941.63
  5341.6  942.76  5348.3  941.43  5355.8  942.93  5390.9  942.37  5457.4  946.92
#Mann=7,-1,0
  4547.8    0.05       0  4773.7    0.12       0  4918.6    0.05       0
  4952.3    0.05       0  4992.2    0.05       0  5055.3    0.12       0
  5227.0    0.05       0
Bank Sta=4952.3,4992.2
Exp/Cntr=0.3,0.1

Type RM Length L Ch R = 1,5276,358,358,358
BEGIN DESCRIPTION:
WHITE CREEK 8.0
END DESCRIPTION:
XS GIS Cut Line= 3
      2878381.43     10165526.11      2878732.76     10164925.66
      2878726.37     10164622.21
#Sta/Elev= 30
  4487.0  931.92  4644.9  926.87  4675.9  926.56  4688.4  924.26  4756.0  919.90
  4814.9  916.64  4837.1  914.25  4849.6  911.60  4875.5  910.67  4885.9  909.36
  4895.8  905.88  4909.7  903.08  4930.7  899.52  4991.9  898.24  4992.9  895.24
  5030.8  895.24  5031.8  898.24  5034.6  904.20  5046.6  910.16  5077.6  916.04
  5083.4  918.20  5108.9  921.65  5136.2  924.31  5173.4  930.01  5179.2  929.82
  5275.3  939.53  5285.7  941.52  5324.3  943.83  5385.3  945.02  5486.2  943.32
#Mann=9,-1,0
  4487.0    0.05       0  4644.9    0.12       0  4756.0    0.05       0
  4875.5    0.12       0  4909.7    0.05       0  4991.9    0.05       0
  5031.8    0.05       0  5108.9    0.12       0  5324.3    0.05       0
Bank Sta=4991.9,5031.8
Exp/Cntr=0.3,0.1

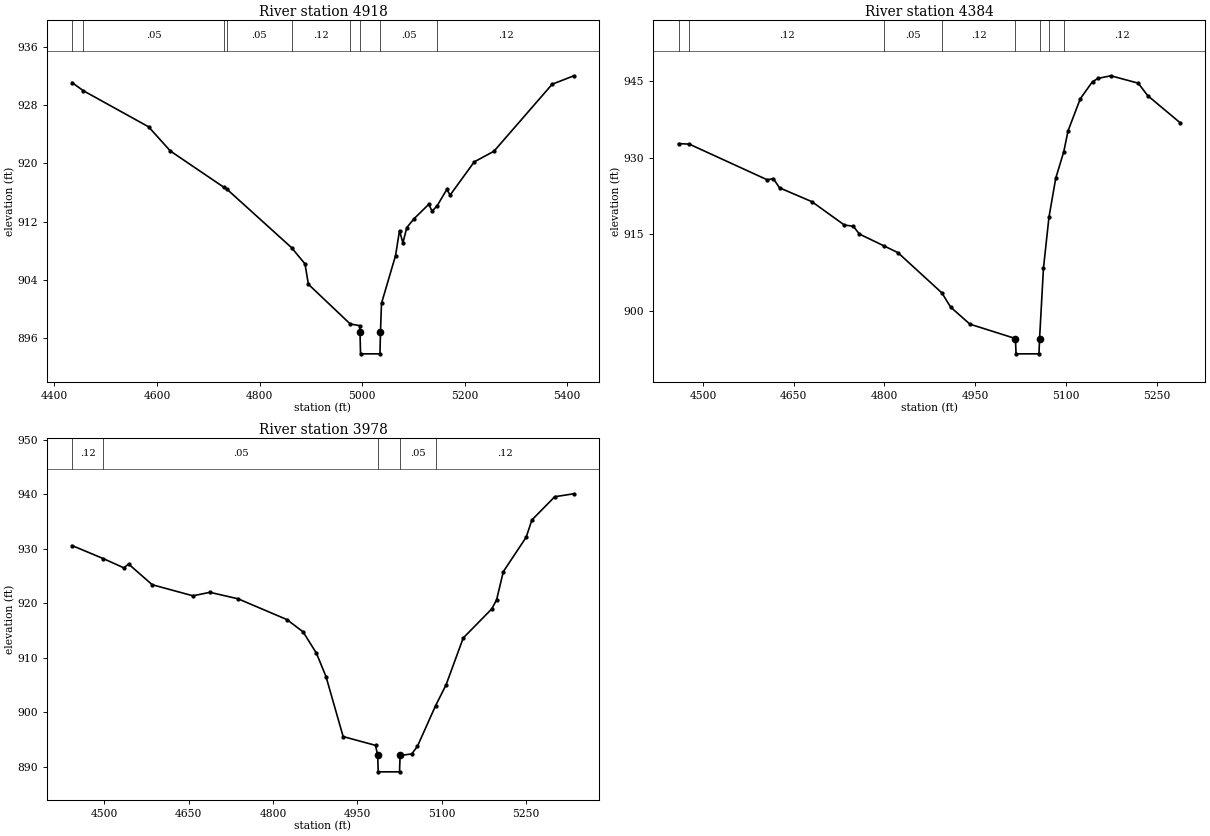
Type RM Length L Ch R = 1,4918,534,534,534
BEGIN DESCRIPTION:
WHITE CREEK 7.0
END DESCRIPTION:
XS GIS Cut Line= 3
      2878467.64     10165695.41      2879063.15     10165182.66
      2879205.72     10165053.08
#Sta/Elev= 30
  4434.5  931.10  4456.7  929.98  4583.6  925.04  4626.4  921.70  4730.4  916.74
  4736.8  916.45  4862.6  908.44  4888.7  906.22  4895.3  903.42  4976.9  897.97
  4995.1  897.74  4996.0  896.87  4997.0  893.87  5034.9  893.87  5035.9  896.87
  5037.9  900.80  5065.3  907.36  5073.0  910.79  5079.6  909.10  5087.3  911.21
  5101.5  912.43  5130.0  914.39  5136.6  913.46  5146.3  914.18  5165.2  916.43
  5171.8  915.67  5218.7  920.22  5257.2  921.68  5370.7  930.88  5413.0  932.04
#Mann=9,-1,0
  4434.5    0.12       0  4456.7    0.05       0  4730.4    0.12       0
  4736.8    0.05       0  4862.6    0.12       0  4976.9    0.05       0
  4996.0    0.05       0  5035.9    0.05       0  5146.3    0.12       0
Bank Sta=4996,5035.9
Exp/Cntr=0.3,0.1

Type RM Length L Ch R = 1,4384,406,406,406
BEGIN DESCRIPTION:
WHITE CREEK 6.0
END DESCRIPTION:
XS GIS Cut Line= 3
      2878461.31     10165816.76      2878815.80     10165752.89
      2879278.90     10165829.54
#Sta/Elev= 30
  4459.6  932.77  4477.4  932.67  4606.3  925.67  4616.3  925.91  4626.6  924.10
  4680.0  921.39  4733.6  916.82  4748.6  916.55  4758.7  915.03  4798.7  912.75
  4822.3  911.39  4895.0  903.50  4909.4  900.72  4941.3  897.37  5016.6  894.55
  5017.6  891.55  5055.5  891.55  5056.5  894.55  5062.9  908.33  5072.0  918.31
  5083.2  925.97  5096.5  931.18  5103.5  935.25  5123.8  941.56  5144.0  944.92
  5153.5  945.57  5174.4  946.07  5219.6  944.62  5235.3  942.17  5289.2  936.83
#Mann=8,-1,0
  4459.6    0.05       0  4477.4    0.12       0  4798.7    0.05       0
  4895.0    0.12       0  5016.6    0.07       0  5056.5    0.12       0
  5072.0    0.05       0  5096.5    0.12       0
Bank Sta=5016.6,5056.5
Exp/Cntr=0.3,0.1

Type RM Length L Ch R = 1,3978,452,452,452
BEGIN DESCRIPTION:
WHITE CREEK 5.0
END DESCRIPTION:
XS GIS Cut Line= 3
      2878368.66     10165931.75      2878636.94     10166107.41
      2879199.08     10166212.81
#Sta/Elev= 30
  4442.6  930.60  4498.1  928.21  4534.7  926.51  4543.1  927.21  4585.2  923.41
  4657.6  921.38  4687.8  922.02  4737.9  920.83  4824.7  917.02  4853.6  914.76
  4877.3  910.84  4894.3  906.56  4924.8  895.55  4982.4  893.94  4986.2  892.08
  4987.2  889.08  5025.1  889.08  5026.1  892.08  5046.9  892.37  5057.0  893.78
  5089.1  901.19  5107.9  905.05  5138.4  913.64  5189.3  918.99  5197.8  920.66
  5209.7  925.81  5250.4  932.13  5260.5  935.29  5301.2  939.56  5335.2  940.10
#Mann=5,-1,0
  4442.6    0.12       0  4498.1    0.05       0  4986.2    0.05       0
  5026.1    0.05       0  5089.1    0.12       0
Bank Sta=4986.2,5026.1
Exp/Cntr=0.3,0.1