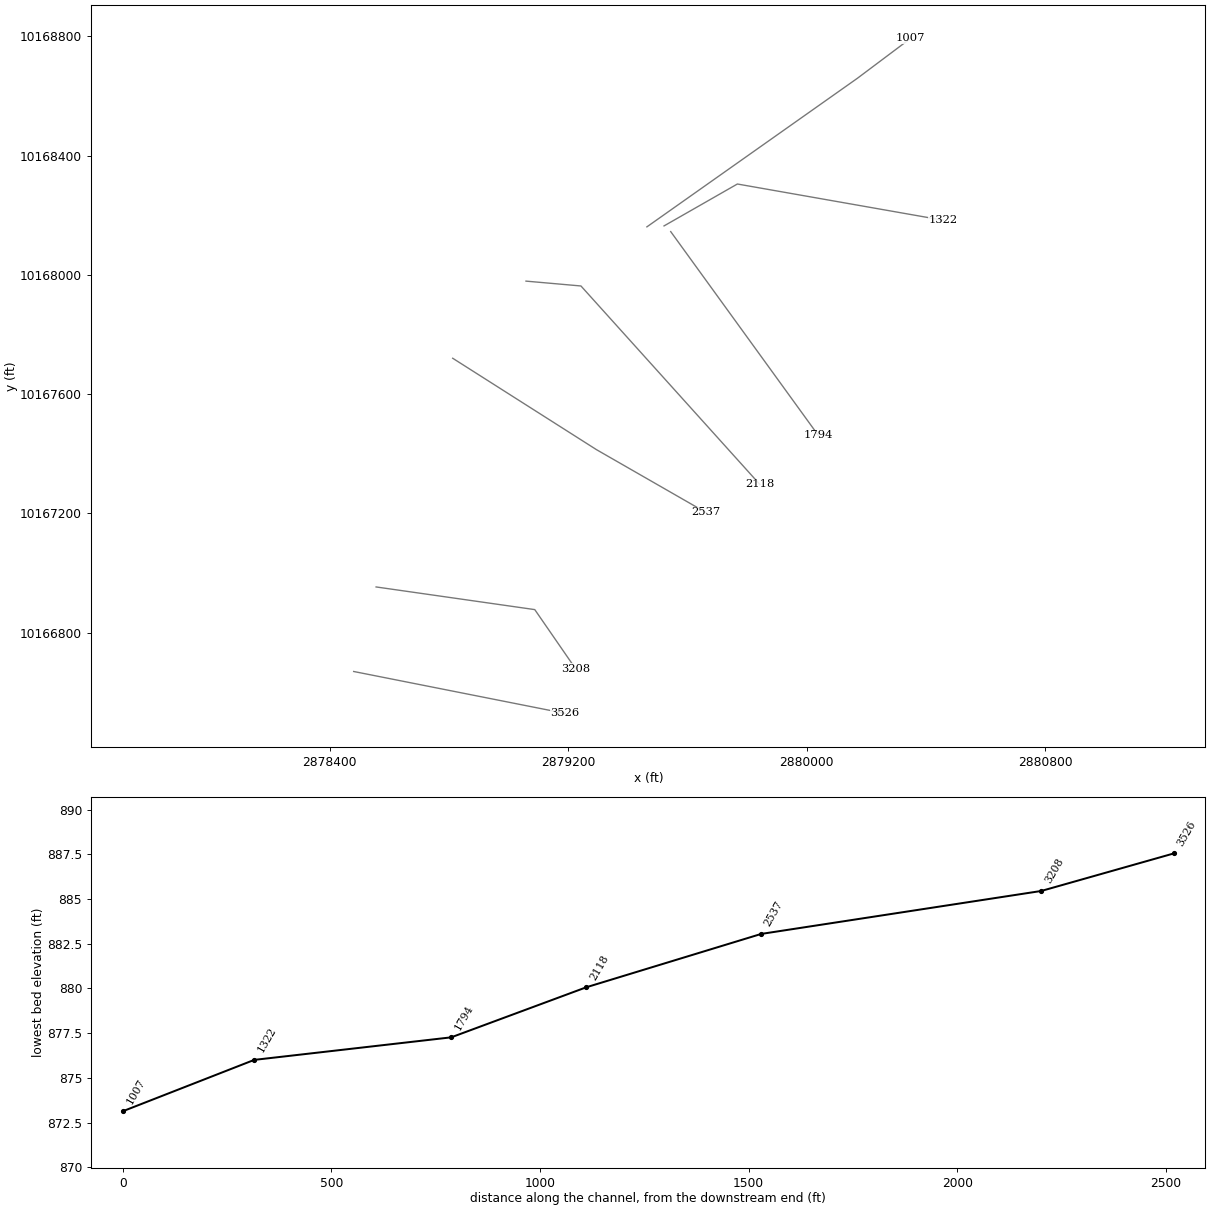
HEC-RAS study WHITE CREEK.prj: WHITE CREEK Base Level Engineering

--- WHITE CREEK.g01 (geometry) --- (continued)

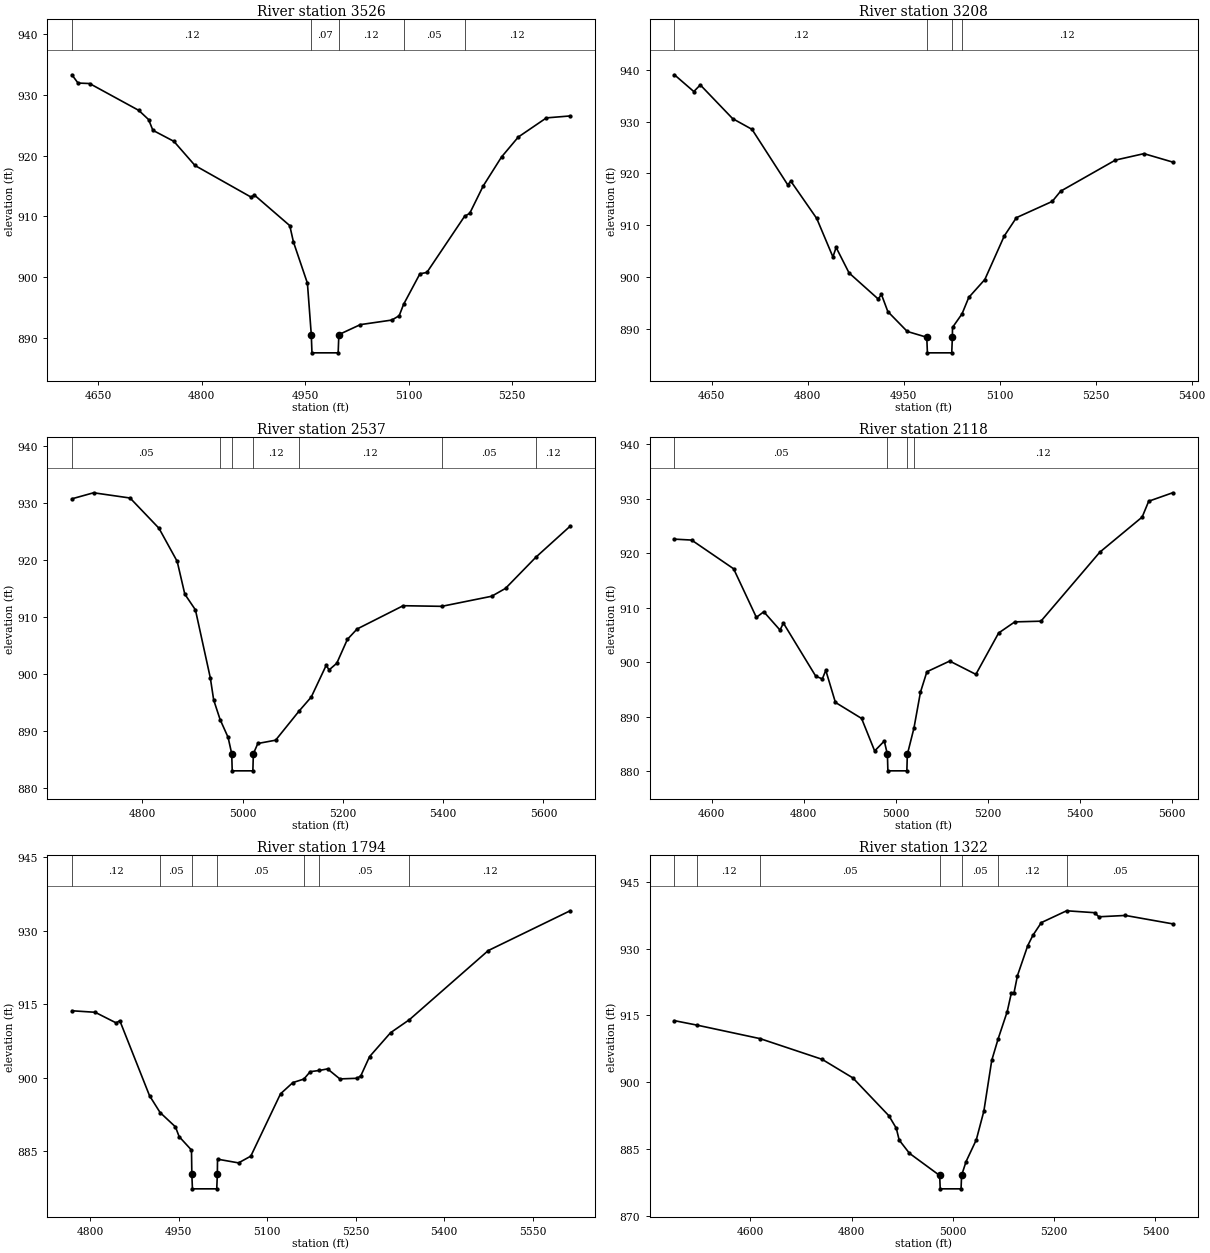
Type RM Length L Ch R = 1,3526,318,318,318
BEGIN DESCRIPTION:
Mapping XS 81f837a0
END DESCRIPTION:
XS GIS Cut Line= 2
      2878480.46     10166669.53      2879189.47     10166529.01
#Sta/Elev= 30
  4611.6  933.28  4620.5  931.92  4637.3  931.84  4708.7  927.42  4722.9  925.91
  4729.1  924.15  4759.6  922.33  4790.2  918.36  4871.4  913.17  4876.5  913.49
  4927.7  908.47  4933.0  905.79  4953.3  899.00  4958.9  890.55  4959.9  887.55
  4997.9  887.55  4998.9  890.55  5030.1  892.19  5075.7  892.94  5086.4  893.65
  5092.8  895.52  5116.5  900.55  5126.6  900.77  5181.2  909.99  5188.8  910.50
  5208.2  914.97  5234.9  919.76  5259.2  923.04  5300.0  926.19  5334.4  926.51
#Mann=5,-1,0
  4611.6    0.12       0  4958.9    0.07       0  4998.9    0.12       0
  5092.8    0.05       0  5181.2    0.12       0
Bank Sta=4958.9,4998.9
Exp/Cntr=0.3,0.1

Type RM Length L Ch R = 1,3208,671,671,671
BEGIN DESCRIPTION:
WHITE CREEK 4.0
END DESCRIPTION:
XS GIS Cut Line= 3
      2878555.65     10166953.12      2879087.95     10166877.12
      2879224.63     10166679.10
#Sta/Elev= 30
  4591.9  939.00  4622.2  935.77  4632.3  937.05  4682.8  930.56  4713.1  928.49
  4768.8  917.83  4773.8  918.50  4814.2  911.33  4839.5  903.92  4844.5  905.75
  4864.7  900.84  4910.2  895.82  4915.3  896.69  4925.3  893.39  4955.6  889.57
  4986.1  888.45  4987.1  885.45  5025.1  885.45  5026.1  888.45  5026.3  890.34
  5041.2  892.96  5051.7  896.12  5076.8  899.57  5107.1  907.94  5126.1  911.48
  5182.1  914.61  5195.2  916.58  5280.8  922.57  5325.4  923.81  5370.2  922.19
#Mann=4,-1,0
  4591.9    0.12       0  4986.1    0.07       0  5026.1    0.12       0
  5041.2    0.12       0
Bank Sta=4986.1,5026.1
Exp/Cntr=0.3,0.1

Type RM Length L Ch R = 1,2537,419,419,419
BEGIN DESCRIPTION:
WHITE CREEK 3.0
END DESCRIPTION:
XS GIS Cut Line= 3
      2878812.60     10167720.34      2879294.89     10167413.72
      2879661.41     10167203.36
#Sta/Elev= 30
  4659.2  930.79  4702.5  931.85  4775.3  930.93  4832.9  925.63  4869.3  919.81
  4884.5  914.06  4905.7  911.30  4935.4  899.37  4942.1  895.49  4954.9  892.06
  4970.9  888.92  4978.1  886.05  4979.1  883.05  5020.3  883.05  5021.3  886.05
  5030.2  887.85  5065.7  888.43  5112.5  893.54  5136.8  896.00  5166.5  901.55
  5172.5  900.77  5187.7  901.93  5208.9  906.12  5228.2  907.94  5320.2  912.03
  5397.2  911.92  5496.8  913.69  5524.4  915.07  5585.2  920.56  5653.3  925.98
#Mann=7,-1,0
  4659.2    0.05       0  4954.9    0.12       0  4978.1    0.03       0
  5021.3    0.12       0  5112.5    0.12       0  5397.2    0.05       0
  5585.2    0.12       0
Bank Sta=4978.1,5021.3
Exp/Cntr=0.3,0.1

Type RM Length L Ch R = 1,2118,324,324,324
BEGIN DESCRIPTION:
WHITE CREEK 2.0
END DESCRIPTION:
XS GIS Cut Line= 3
      2879058.51     10167979.04      2879242.89     10167962.76
      2879843.09     10167296.82
#Sta/Elev= 30
  4519.2  922.60  4556.5  922.43  4647.7  917.16  4697.1  908.24  4713.2  909.27
  4748.4  905.91  4755.8  907.19  4826.1  897.43  4840.3  896.95  4847.8  898.52
  4868.7  892.63  4925.5  889.69  4953.9  883.72  4974.8  885.54  4981.6  883.07
  4982.6  880.07  5023.8  880.07  5024.8  883.07  5039.2  887.92  5053.3  894.50
  5067.3  898.26  5116.8  900.22  5173.6  897.78  5223.0  905.37  5258.1  907.41
  5314.9  907.54  5442.7  920.21  5534.6  926.65  5548.8  929.56  5600.8  931.11
#Mann=4,-1,0
  4519.2    0.05       0  4981.6    0.05       0  5024.8    0.05       0
  5039.2    0.12       0
Bank Sta=4981.6,5024.8
Exp/Cntr=0.3,0.1

Type RM Length L Ch R = 1,1794,472,472,472
BEGIN DESCRIPTION:
Mapping XS 78880c0e
END DESCRIPTION:
XS GIS Cut Line= 2
      2879543.99     10168145.15      2880039.08     10167461.62
#Sta/Elev= 30
  4769.3  913.64  4808.7  913.33  4844.3  911.16  4850.5  911.61  4900.8  896.30
  4918.7  892.86  4944.7  889.93  4951.0  887.93  4971.9  885.19  4972.5  880.27
  4973.5  877.27  5014.7  877.27  5015.7  880.27  5016.0  883.33  5051.6  882.57
  5072.4  883.95  5122.7  896.67  5143.6  898.97  5162.3  899.69  5173.0  901.20
  5188.7  901.45  5202.4  901.77  5223.2  899.72  5252.6  899.85  5258.8  900.37
  5273.5  904.26  5309.1  909.15  5341.2  911.83  5474.6  925.93  5613.3  934.06
#Mann=7,-1,0
  4769.3    0.12       0  4918.7    0.05       0  4972.5    0.05       0
  5015.7    0.05       0  5162.3    0.12       0  5188.7    0.05       0
  5341.2    0.12       0
Bank Sta=4972.5,5015.7
Exp/Cntr=0.3,0.1

Type RM Length L Ch R = 1,1322,315,315,315
BEGIN DESCRIPTION:
Mapping XS 3cc920a5
END DESCRIPTION:
XS GIS Cut Line= 3
      2879521.61     10168164.26      2879767.59     10168304.82
      2880457.49     10168183.45
#Sta/Elev= 30
  4450.1  913.83  4494.9  912.82  4619.5  909.78  4741.6  905.14  4802.5  900.95
  4873.6  892.44  4888.2  889.64  4893.9  886.98  4914.2  884.00  4973.9  879.01
  4974.9  876.01  5016.1  876.01  5017.1  879.01  5025.9  882.12  5046.2  887.04
  5061.1  893.48  5076.7  904.91  5089.5  909.80  5107.2  915.85  5115.3  920.00
  5120.4  919.94  5127.5  923.97  5147.8  930.71  5157.9  933.01  5174.6  935.88
  5224.5  938.54  5279.8  938.11  5288.2  937.19  5340.7  937.49  5433.9  935.60
#Mann=7,-1,0
  4450.1    0.05       0  4494.9    0.12       0  4619.5    0.05       0
  4973.9    0.05       0  5017.1    0.05       0  5089.5    0.12       0
  5224.5    0.05       0
Bank Sta=4973.9,5017.1
Exp/Cntr=0.3,0.1

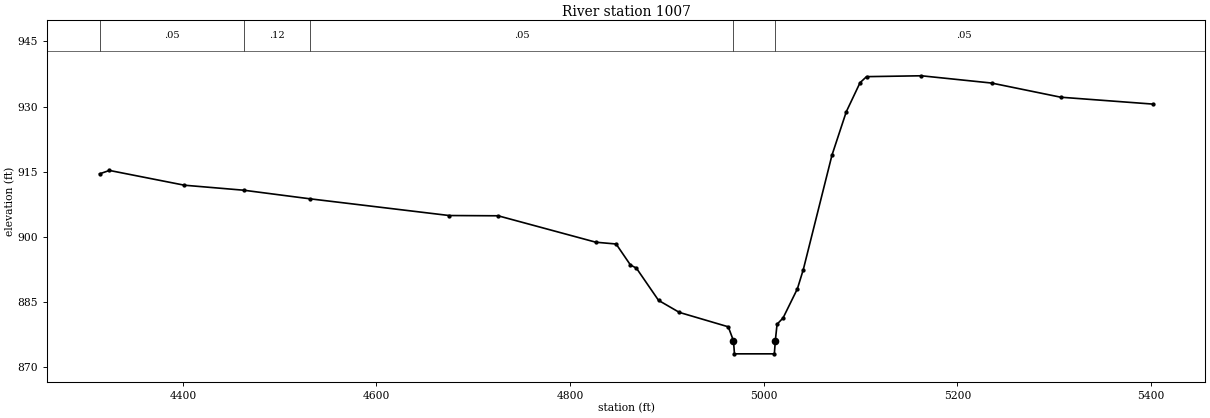
Type RM Length L Ch R = 1,1007,0,0,0
BEGIN DESCRIPTION:
WHITE CREEK 1.0
END DESCRIPTION:
XS GIS Cut Line= 3
      2879464.14     10168161.08      2880170.02     10168659.34
      2880348.88     10168793.49
#Sta/Elev= 30
  4314.1  914.54  4324.2  915.32  4401.7  911.92  4462.9  910.77  4531.1  908.80
  4675.1  904.95  4725.6  904.89  4826.6  898.81  4847.5  898.40  4862.3  893.57
  4868.4  892.86  4891.3  885.44  4912.8  882.67  4963.3  879.36  4968.7  876.14
  4969.7  873.14  5010.9  873.14  5011.9  876.14  5013.7  879.95  5019.9  881.39
  5034.7  888.10  5040.8  892.52  5070.4  918.83  5085.2  928.82  5099.4  935.50
  5106.1  936.89  5162.7  937.09  5235.2  935.42  5306.7  932.16  5401.7  930.58
#Mann=5,-1,0
  4314.1    0.05       0  4462.9    0.12       0  4531.1    0.05       0
  4968.7    0.05       0  5011.9    0.05       0
Bank Sta=4968.7,5011.9
Exp/Cntr=0.3,0.1

Chan Stop Cuts=-1