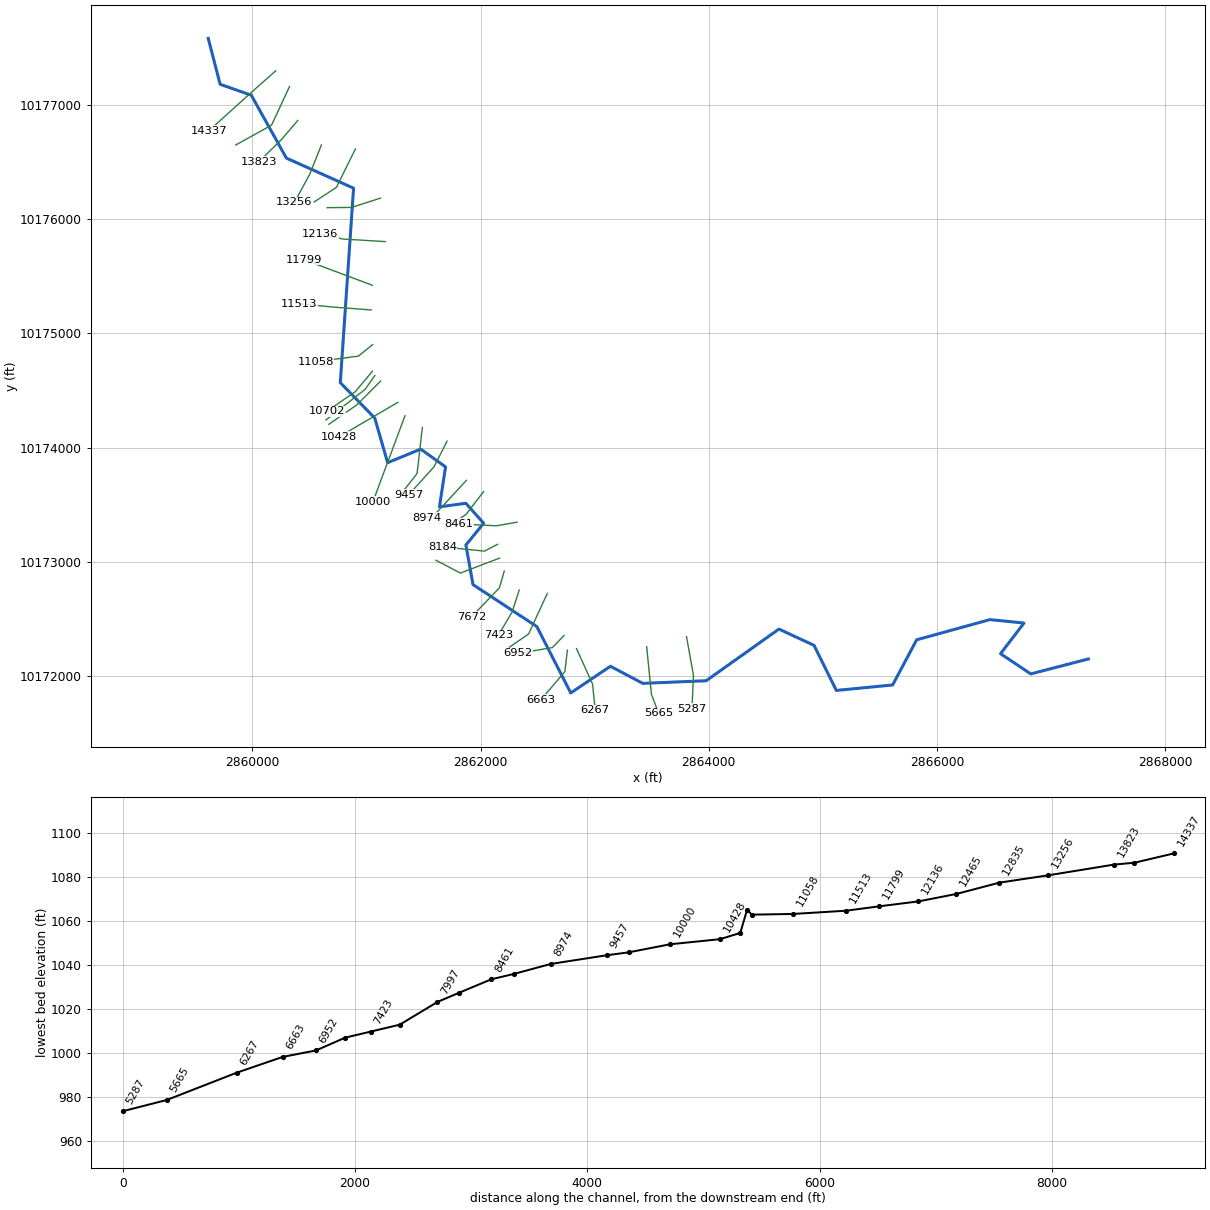
--- SOUTH PRONG CREEK.prj (project) ---

Proj Title=SOUTH PRONG CREEK Base Level Engineering
Current Plan=p01
Default Exp/Contr=0.3,0.1
English Units
Geom File=g01
Flow File=f01
Plan File=p01
Y Axis Title=Elevation
X Axis Title(PF)=Main Channel Distance
X Axis Title(XS)=Station
BEGIN DESCRIPTION:
SOUTH PRONG CREEK
END DESCRIPTION:
DSS Export Rating Curves= 0
DSS Export Rating Curve Sorted= 0
DSS Export Volume Flow Curves= 0
DXF OffsetX= 0
DXF OffsetY= 0
DXF ScaleX= 1
DXF ScaleY= 10

--- SOUTH PRONG CREEK.p01 (plan) ---

Plan Title=Multiple Run
Short Identifier=Multiple
Geom File=g01
Flow File=f01
Subcritical Flow
K Sum by GR= 0
Std Step Tol= 0.01
Critical Tol= 0.01
Num of Std Step Trials= 20
Max Error Tol= 0.3
Flow Tol Ratio= 0.001
Split Flow NTrial= 30
Split Flow Tol= 0.02
Split Flow Ratio= 0.02
Log Output Level= 0
Friction Slope Method= 1
Unsteady Friction Slope Method= 2
Unsteady Bridges Friction Slope Method= 1
Parabolic Critical Depth
Global Vel Dist=  1 , 1 , 1
Global Log Level= 0
CheckData=True
Encroach Param= -1, 0, 0, 0
BEGIN DESCRIPTION:
Multiple Run
END DESCRIPTION:

--- SOUTH PRONG CREEK.f01 (steady flow) ---

Flow Title=Multiple
Number of Profiles=7
Profile Names=10-year,25-year,50-year,1pct_min,100-year,1pct_plu,500-year
River Rch & RM= SOUTH PRONG CREE,Reach-1,14337
      81     159     252     132     398    1202    1066
River Rch & RM= SOUTH PRONG CREE,Reach-1,1702
      85     166     263     138     417    1260    1122
River Rch & RM= SOUTH PRONG CREE,Reach-1,162
     252     559     937     514    1552    4688    4531
Boundary for River Rch & Prof#=SOUTH PRONG CREE,Reach-1,1
Up Type=0
Dn Type=3
Dn Slope=0.005
Boundary for River Rch & Prof#=SOUTH PRONG CREE,Reach-1,2
Up Type=0
Dn Type=3
Dn Slope=0.005
Boundary for River Rch & Prof#=SOUTH PRONG CREE,Reach-1,3
Up Type=0
Dn Type=3
Dn Slope=0.005
Boundary for River Rch & Prof#=SOUTH PRONG CREE,Reach-1,4
Up Type=0
Dn Type=3
Dn Slope=0.005
Boundary for River Rch & Prof#=SOUTH PRONG CREE,Reach-1,5
Up Type=0
Dn Type=3
Dn Slope=0.005
Boundary for River Rch & Prof#=SOUTH PRONG CREE,Reach-1,6
Up Type=0
Dn Type=3
Dn Slope=0.005
Boundary for River Rch & Prof#=SOUTH PRONG CREE,Reach-1,7
Up Type=0
Dn Type=3
Dn Slope=0.005

--- SOUTH PRONG CREEK.g01 (geometry) ---

Geom Title=Existing Conditions
Program Version=4.10

River Reach=SOUTH PRONG CREE,Reach-1
Reach XY= 30
        2859614.       10177588.       2859718.5       10177185.
       2859991.5       10177089.      2860298.75       10176538.
       2860887.5       10176274.      2860771.25       10174569.
       2861073.5       10174258.      2861185.75       10173867.
        2861476.       10173986.      2861693.25       10173830.
      2861640.25       10173480.       2861871.5       10173511.
       2862027.5       10173336.       2861871.5       10173145.
        2861934.       10172798.      2862493.25       10172430.
      2862790.25       10171848.      2863137.75       10172082.
      2863421.75       10171932.        2863977.       10171955.
       2864614.5       10172408.       2864922.5       10172265.
      2865117.25       10171870.        2865611.       10171918.
      2865821.25       10172314.      2866463.25       10172491.
      2866761.75       10172461.      2866556.25       10172192.
      2866821.25       10172015.      2867325.75       10172146.

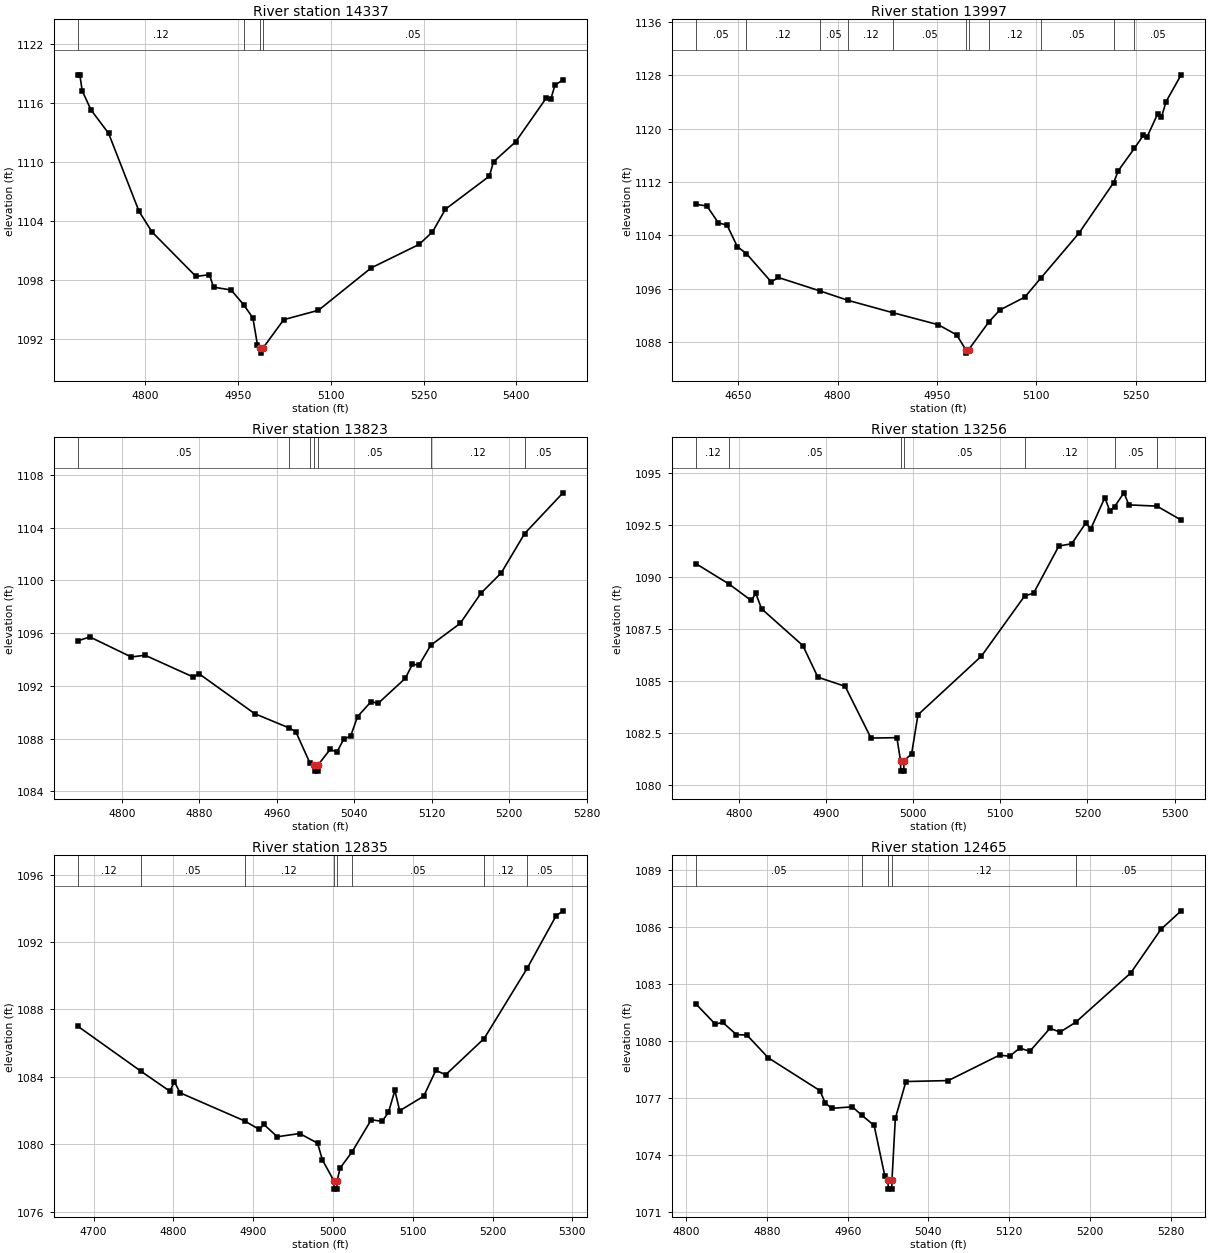
Type RM Length L Ch R = 1 ,14337   ,340,340,340
BEGIN DESCRIPTION:
SOUTH PRONG CREEK 31.0
END DESCRIPTION:
XS GIS Cut Line= 3
      2860205.69     10177303.12      2860008.17     10177128.62
      2859621.49     10176778.94
#Sta/Elev= 30
  4690.6 1118.85  4693.9 1118.85  4697.7 1117.24  4711.9 1115.29  4740.4 1112.91
  4789.7 1104.98  4810.7 1102.89  4881.7 1098.38  4903.5 1098.55  4910.2 1097.29
  4938.6    1097  4959.1 1095.49  4973.8 1094.17  4981.2 1091.44    4986 1091.09
  4986.2 1090.59    4990 1091.09  5023.8 1093.99  5079.9 1094.94  5165.1 1099.24
  5242.8 1101.63  5264.4  1102.9  5285.4 1105.21  5356.4 1108.56  5363.1 1110.02
  5398.9 1112.05  5448.3 1116.48  5455.7 1116.35  5462.5 1117.81  5475.5 1118.33
#Mann= 4 ,-1 , 0
  4690.6     .12       0  4959.1     .05       0    4986     .05       0
    4990     .05       0
Bank Sta=4986,4990
XS Rating Curve= 0 ,0
Exp/Cntr=0.3,0.1

Type RM Length L Ch R = 1 ,13997   ,174,174,174
BEGIN DESCRIPTION:
SOUTH PRONG CREEK 30.0
END DESCRIPTION:
XS GIS Cut Line= 3
      2860326.41     10177165.67      2860169.13     10176827.04
      2859855.72     10176653.13
#Sta/Elev= 30
  4586.5 1108.66    4603 1108.41  4620.4 1105.87  4633.4 1105.55  4648.8 1102.33
  4662.7 1101.26  4700.1 1097.02  4710.6  1097.7  4773.3 1095.69  4815.8 1094.27
  4883.8 1092.41  4951.9 1090.62  4979.6  1089.1  4993.6 1086.86  4993.9 1086.36
  4997.6 1086.86  5028.4 1091.05  5044.8 1092.82  5082.6 1094.76  5106.3 1097.57
  5163.9 1104.31  5216.6 1111.93  5223.4 1113.69  5247.9 1117.07  5261.1 1118.98
  5266.8 1118.75  5282.9 1122.22  5288.6 1121.71  5295.5 1124.05  5318.3 1128.07
#Mann= 11 ,-1 , 0
  4586.5     .05       0  4662.7     .12       0  4773.3     .05       0
  4815.8     .12       0  4883.8     .05       0  4993.6     .03       0
  4997.6     .05       0  5028.4     .12       0  5106.3     .05       0
  5216.6     .12       0  5247.9     .05       0
Bank Sta=4993.6,4997.6
XS Rating Curve= 0 ,0
Exp/Cntr=0.3,0.1

Type RM Length L Ch R = 1 ,13823   ,567,567,567
BEGIN DESCRIPTION:
SOUTH PRONG CREEK 29.0
END DESCRIPTION:
XS GIS Cut Line= 3
      2860398.55     10176867.74      2860259.79     10176704.93
      2860055.65     10176503.08
#Sta/Elev= 30
  4754.5 1095.41  4766.9 1095.71  4809.7 1094.19    4824 1094.32  4873.4 1092.68
    4880  1092.9  4937.1 1089.89  4972.9  1088.8  4979.7 1088.51  4994.2 1086.14
  4998.9 1086.03  4999.2 1085.53  5002.7 1085.53  5002.9 1086.03  5015.1 1087.18
  5022.1 1086.98  5029.2 1087.97  5036.2 1088.18  5043.4 1089.67  5057.5 1090.81
  5064.5 1090.66  5092.8 1092.58  5099.9 1093.62    5107 1093.59    5119 1095.08
  5149.4 1096.74  5170.6 1099.01  5191.8 1100.57  5215.9 1103.55  5255.5 1106.64
#Mann= 7 ,-1 , 0
  4754.5     .05       0  4972.9     .12       0  4994.2     .05       0
  4998.9     .05       0  5002.9     .05       0    5119     .12       0
  5215.9     .05       0
Bank Sta=4998.9,5002.9
XS Rating Curve= 0 ,0
Exp/Cntr=0.3,0.1

Type RM Length L Ch R = 1 ,13256   ,421,421,421
BEGIN DESCRIPTION:
SOUTH PRONG CREEK 28.0
END DESCRIPTION:
XS GIS Cut Line= 3
      2860605.68     10176653.09      2860504.01     10176397.81
      2860369.82     10176149.65
#Sta/Elev= 30
  4750.7 1090.64  4788.7 1089.66  4814.1 1088.87  4819.4 1089.21    4826 1088.47
  4873.4  1086.7  4890.6 1085.18  4921.9 1084.74  4951.6 1082.25  4981.3 1082.27
  4985.5 1081.16  4985.7 1080.66  4989.2 1080.66  4989.5 1081.16  4998.2 1081.49
  5005.5 1083.37  5078.3 1086.19    5128 1089.09  5138.2 1089.22  5167.2 1091.49
    5182  1091.6  5198.2  1092.6  5203.8 1092.31    5220 1093.82  5225.7 1093.18
  5231.3 1093.39  5241.9 1094.05  5247.6 1093.47  5279.8 1093.41  5307.6 1092.74
#Mann= 7 ,-1 , 0
  4750.7     .12       0  4788.7     .05       0  4985.5     .03       0
  4989.5     .05       0    5128     .12       0  5231.3     .05       0
  5279.8     .12       0
Bank Sta=4985.5,4989.5
XS Rating Curve= 0 ,0
Exp/Cntr=0.3,0.1

Type RM Length L Ch R = 1 ,12835   ,370,370,370
BEGIN DESCRIPTION:
Mapping XS 1fe32636
END DESCRIPTION:
XS GIS Cut Line= 3
      2860903.63     10176617.96      2860737.13     10176281.25
      2860542.85     10176153.58
#Sta/Elev= 30
  4680.2    1087  4759.3 1084.33  4795.6 1083.14  4801.2 1083.71  4808.3 1083.05
  4889.2 1081.38  4907.8 1080.87  4913.4 1081.17  4930.2 1080.44  4958.3 1080.63
  4980.7 1080.06  4986.8 1079.06  5001.1 1077.83  5001.4 1077.33  5004.9 1077.33
  5005.1 1077.83  5009.1 1078.59  5023.8 1079.53    5048 1081.45  5061.5 1081.35
  5069.5 1081.88  5077.6 1083.19  5083.6 1081.98  5113.8 1082.85  5128.9 1084.38
  5141.3 1084.12  5189.5 1086.27  5243.3 1090.43  5279.5 1093.54  5288.3 1093.85
#Mann= 8 ,-1 , 0
  4680.2     .12       0  4759.3     .05       0  4889.2     .12       0
  5001.1     .07       0  5005.1     .12       0  5023.8     .05       0
  5189.5     .12       0  5243.3     .05       0
Bank Sta=5001.1,5005.1
XS Rating Curve= 0 ,0
Exp/Cntr=0.3,0.1

Type RM Length L Ch R = 1 ,12465   ,329,329,329
BEGIN DESCRIPTION:
SOUTH PRONG CREEK 27.0
END DESCRIPTION:
XS GIS Cut Line= 3
      2861123.85     10176186.91      2860870.34     10176105.49
      2860655.72     10176103.11
#Sta/Elev= 30
  4809.6 1081.95  4828.7 1080.89  4836.1 1080.98  4849.7 1080.34  4860.2 1080.31
  4881.2 1079.12  4932.5 1077.39  4937.7 1076.74  4944.2 1076.46  4964.6 1076.54
  4973.7 1076.11  4986.2 1075.56  4996.7 1072.92  4999.9 1072.71  5000.2 1072.21
  5003.7 1072.21  5003.9 1072.71  5007.2 1075.93  5017.7 1077.87  5059.7 1077.92
  5110.5 1079.26  5120.5  1079.2  5130.5 1079.63  5140.5 1079.46  5160.5 1080.67
  5170.5 1080.47    5186 1080.99  5240.5 1083.58  5270.5 1085.88  5290.5 1086.85
#Mann= 5 ,-1 , 0
  4809.6     .05       0  4973.7     .12       0  4999.9     .07       0
  5003.9     .12       0    5186     .05       0
Bank Sta=4999.9,5003.9
XS Rating Curve= 0 ,0
Exp/Cntr=0.3,0.1

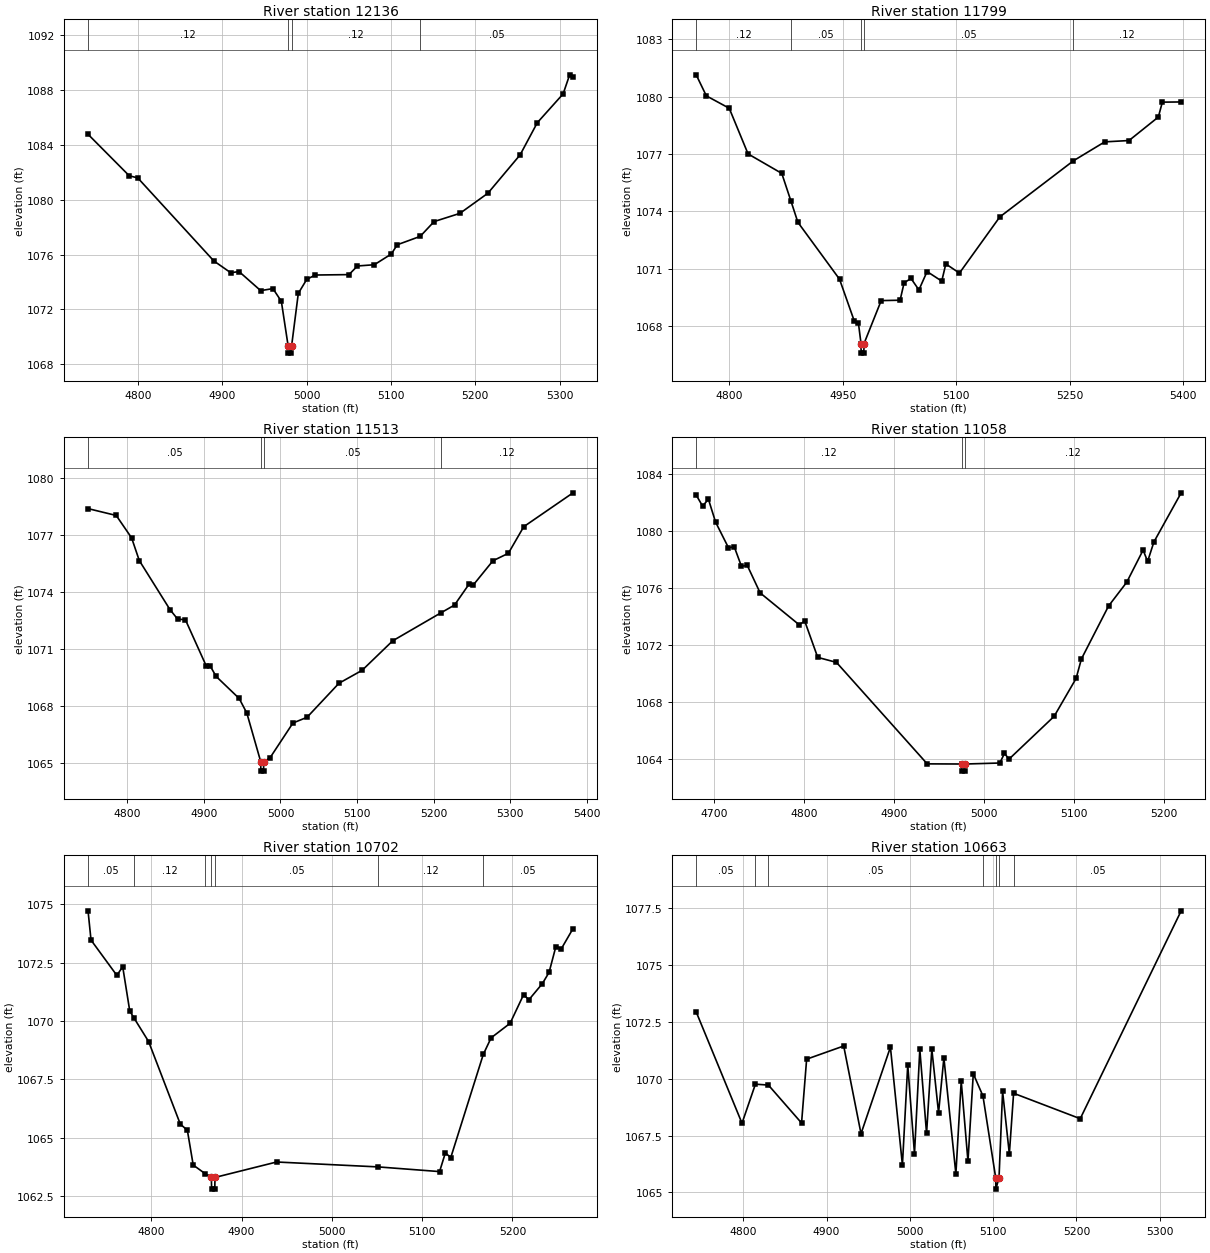
Type RM Length L Ch R = 1 ,12136   ,337,337,337
BEGIN DESCRIPTION:
SOUTH PRONG CREEK 26.0
END DESCRIPTION:
XS GIS Cut Line= 3
      2861164.51     10175805.76      2860796.33     10175827.96
      2860594.18     10175868.39
#Sta/Elev= 30
  4740.9 1084.78  4789.8 1081.75  4799.8  1081.6    4890 1075.54    4910 1074.68
    4920 1074.76  4945.6 1073.37  4960.1 1073.52  4970.1 1072.59  4978.2 1069.31
  4978.4 1068.81  4981.9 1068.81  4982.2 1069.31  4990.2 1073.17  5000.2 1074.19
  5010.2 1074.51  5050.3 1074.54  5060.3 1075.17  5080.3 1075.26  5100.4 1076.04
  5107.6 1076.72  5134.7 1077.33  5151.2 1078.41  5181.8 1079.01    5215 1080.48
  5253.2 1083.28  5273.6 1085.63  5304.2 1087.73  5311.9 1089.12  5315.9 1088.96
#Mann= 4 ,-1 , 0
  4740.9     .12       0  4978.2     .07       0  4982.2     .12       0
  5134.7     .05       0
Bank Sta=4978.2,4982.2
XS Rating Curve= 0 ,0
Exp/Cntr=0.3,0.1

Type RM Length L Ch R = 1 ,11799   ,286,286,286
BEGIN DESCRIPTION:
Mapping XS e233f77a
END DESCRIPTION:
XS GIS Cut Line= 2
      2861051.64     10175422.78      2860451.06     10175648.23
#Sta/Elev= 30
    4756 1081.15  4769.4 1080.05  4799.7  1079.4  4824.6 1077.01  4869.2 1075.99
  4881.5 1074.52  4890.5 1073.43  4945.6 1070.45  4965.2 1068.25  4970.5 1068.18
    4974 1067.08  4974.2 1066.58  4977.7 1066.58    4978 1067.08  5000.7 1069.33
  5025.7 1069.35    5031 1070.26  5040.1 1070.49  5050.6 1069.89  5061.4 1070.85
  5080.8 1070.35  5086.2 1071.25  5104.2 1070.77  5157.6 1073.71    5255 1076.65
  5296.4 1077.64  5328.5 1077.71  5367.3 1078.94  5372.6 1079.72  5397.5 1079.73
#Mann= 5 ,-1 , 0
    4756     .12       0  4881.5     .05       0    4974     .05       0
    4978     .05       0    5255     .12       0
Bank Sta=4974,4978
XS Rating Curve= 0 ,0
Exp/Cntr=0.3,0.1

Type RM Length L Ch R = 1 ,11513   ,455,455,455
BEGIN DESCRIPTION:
SOUTH PRONG CREEK 25.0
END DESCRIPTION:
XS GIS Cut Line= 3
      2861042.39     10175206.31      2860698.11     10175232.32
      2860411.75     10175261.44
#Sta/Elev= 30
  4748.8 1078.39  4785.6 1078.03  4805.7 1076.85  4815.7 1075.66  4855.8 1073.08
  4865.8 1072.58  4875.9 1072.55  4903.2 1070.11  4908.2 1070.12    4916 1069.57
  4946.1 1068.41  4956.1 1067.64  4974.2 1065.09  4974.4 1064.59  4977.9 1064.59
  4978.2 1065.09  4986.2 1065.28  5016.3 1067.12  5034.7 1067.42  5076.4 1069.21
  5106.6 1069.89  5146.5 1071.44  5209.4 1072.91  5227.2 1073.32  5246.2 1074.42
  5251.2 1074.35  5277.4 1075.65  5297.5 1076.04  5317.6 1077.44  5381.9 1079.22
#Mann= 4 ,-1 , 0
  4748.8     .05       0  4974.2     .05       0  4978.2     .05       0
  5209.4     .12       0
Bank Sta=4974.2,4978.2
XS Rating Curve= 0 ,0
Exp/Cntr=0.3,0.1

Type RM Length L Ch R = 1 ,11058   ,356,356,356
BEGIN DESCRIPTION:
SOUTH PRONG CREEK 24.0
END DESCRIPTION:
XS GIS Cut Line= 3
      2861055.65     10174903.08      2860929.54     10174801.13
      2860555.68     10174753.11
#Sta/Elev= 30
  4680.2 1082.52  4687.3 1081.75  4693.8 1082.23  4701.7 1080.63  4716.1 1078.82
  4722.5 1078.89  4730.5 1077.52  4736.9 1077.59  4751.3 1075.65  4794.5 1073.42
  4800.9 1073.66  4815.3 1071.12  4836.1 1070.77    4937 1063.64  4975.3 1063.63
  4975.6 1063.13  4979.1 1063.13  4979.3 1063.63  5017.7  1063.7  5022.9 1064.38
  5027.9 1063.97  5078.1 1066.98  5102.5 1069.64  5108.4 1071.01  5138.6 1074.73
  5158.8  1076.4    5177 1078.66    5182 1077.86    5189 1079.23  5219.3 1082.68
#Mann= 3 ,-1 , 0
  4680.2     .12       0  4975.3     .07       0  4979.3     .12       0
Bank Sta=4975.3,4979.3
XS Rating Curve= 0 ,0
Exp/Cntr=0.3,0.1

Type RM Length L Ch R = 1 ,10702   ,39,39,39
BEGIN DESCRIPTION:
Mapping XS ed5ef794
END DESCRIPTION:
XS GIS Cut Line= 3
      2861053.51     10174669.78      2860901.79     10174488.45
      2860653.83     10174318.22
#Sta/Elev= 30
  4729.9 1074.71  4733.2 1073.46  4761.8 1071.95  4768.3 1072.32  4776.1 1070.43
  4780.6 1070.14    4797 1069.12  4832.1 1065.59  4839.9 1065.33  4846.4 1063.84
    4860 1063.46  4866.5 1063.31  4866.8 1062.81  4870.3 1062.81  4870.5 1063.31
  4938.8 1063.97  5051.3 1063.76  5119.3 1063.56  5125.7 1064.36  5131.7 1064.16
  5167.7 1068.57  5176.4 1069.28  5197.4  1069.9  5212.3 1071.12  5218.3 1070.91
  5233.2  1071.6  5240.6 1072.08  5248.1 1073.18  5254.2 1073.09  5267.1 1073.95
#Mann= 7 ,-1 , 0
  4729.9     .05       0  4780.6     .12       0    4860     .05       0
  4866.5     .03       0  4870.5     .05       0  5051.3     .12       0
  5167.7     .05       0
Bank Sta=4866.5,4870.5
XS Rating Curve= 0 ,0
Exp/Cntr=0.3,0.1

Type RM Length L Ch R = 1 ,10663   ,59,59,59
BEGIN DESCRIPTION:
SOUTH PRONG CREEK 23.0
END DESCRIPTION:
XS GIS Cut Line= 3
      2861073.83     10174630.88      2860989.59     10174510.78
      2860646.49      10174242.4
#Sta/Elev= 30
  4743.4 1072.94  4798.4 1068.04  4814.5 1069.76  4830.1 1069.72  4869.9 1068.05
    4876 1070.86  4920.5 1071.44  4941.3 1067.58  4976.6 1071.39    4991  1066.2
  4997.4 1070.61  5005.5  1066.7  5011.9 1071.29    5020 1067.59  5026.3  1071.3
  5034.4  1068.5  5040.8 1070.92  5055.2 1065.81  5061.6 1069.89  5069.7 1066.37
  5076.1 1070.22  5087.7 1069.24    5103 1065.64  5103.2 1065.14    5107 1065.64
  5111.3 1069.44  5119.4 1066.69  5124.5 1069.36  5204.5 1068.24  5325.7 1077.39
#Mann= 7 ,-1 , 0
  4743.4     .05       0  4814.5     .12       0  4830.1     .05       0
  5087.7     .12       0    5103     .03       0    5107     .12       0
  5124.5     .05       0
Bank Sta=5103,5107
XS Rating Curve= 0 ,0
Exp/Cntr=0.3,0.1

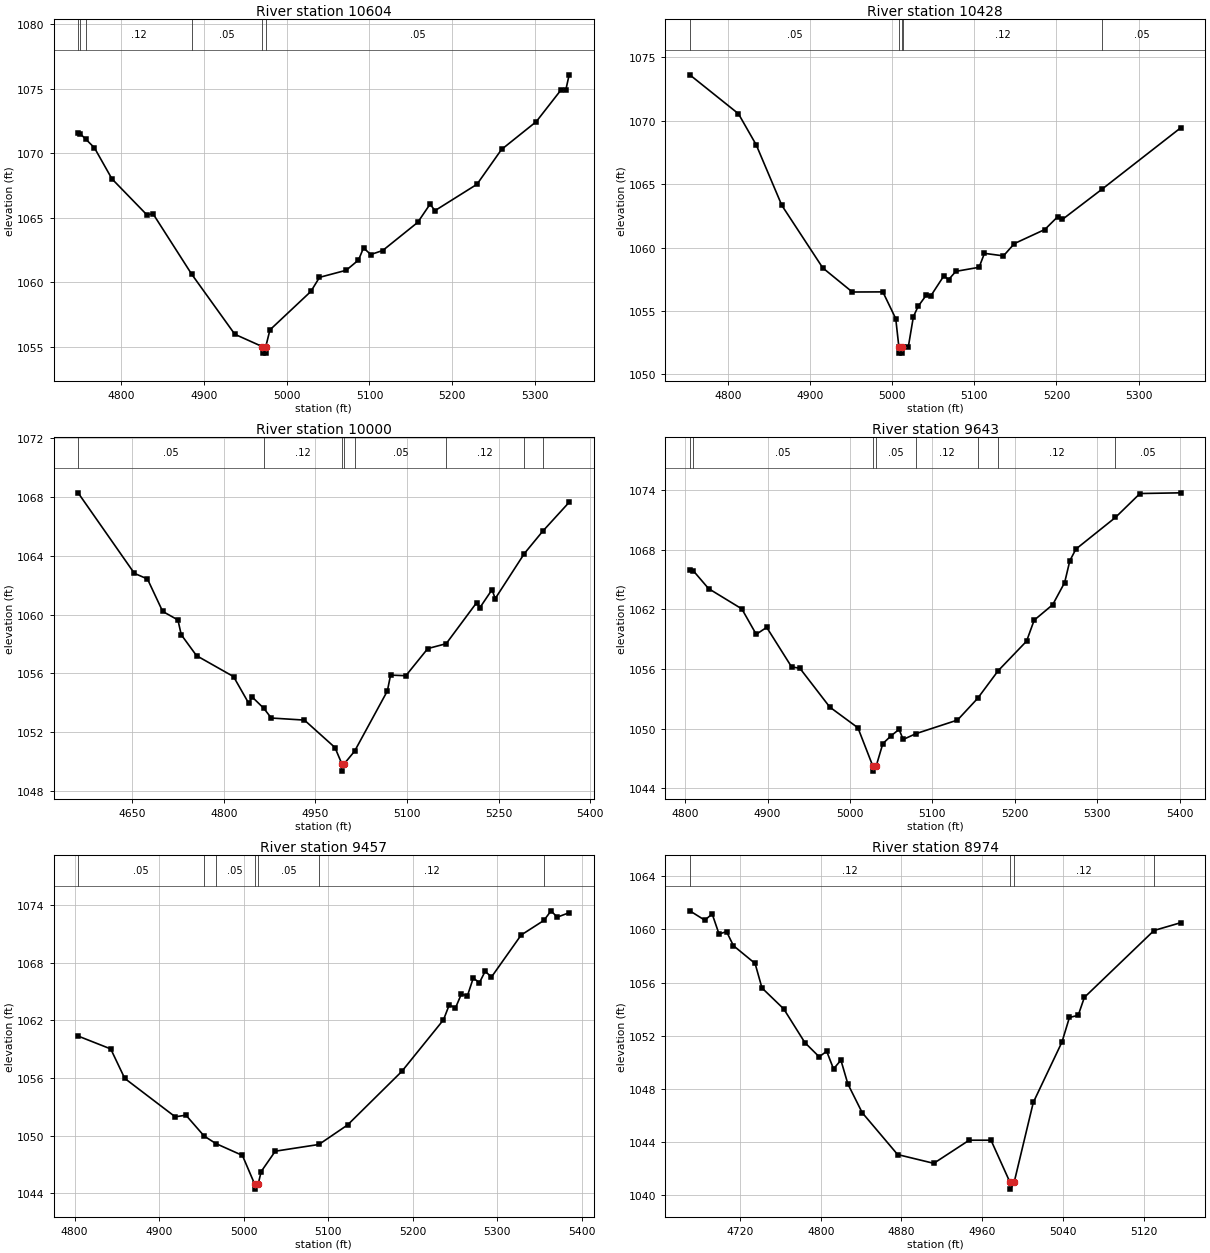
Type RM Length L Ch R = 1 ,10604   ,176,176,176
BEGIN DESCRIPTION:
SOUTH PRONG CREEK 22.0
END DESCRIPTION:
XS GIS Cut Line= 3
      2861123.79      10174582.8      2860918.44      10174375.6
      2860670.61     10174203.59
#Sta/Elev= 30
  4747.9 1071.53  4750.7 1071.49  4757.1 1071.09  4767.6 1070.42  4788.8 1068.01
  4831.2 1065.21  4838.3 1065.32  4885.1 1060.63  4937.3 1055.97  4970.7 1055.01
  4970.9 1054.51  4974.4 1054.51  4974.7 1055.01  4979.7 1056.31  5029.2 1059.29
  5039.6 1060.38  5071.9 1060.93  5086.7 1061.72  5092.8 1062.66  5101.6 1062.15
    5116 1062.46  5158.3 1064.64  5173.2 1066.05  5179.2 1065.55  5229.9 1067.59
  5259.6 1070.29  5301.5 1072.44  5331.2 1074.88  5337.3 1074.92  5341.3 1076.07
#Mann= 6 ,-1 , 0
  4747.9     .12       0  4750.7     .05       0  4757.1     .12       0
  4885.1     .05       0  4970.7     .03       0  4974.7     .05       0
Bank Sta=4970.7,4974.7
XS Rating Curve= 0 ,0
Exp/Cntr=0.3,0.1

Type RM Length L Ch R = 1 ,10428   ,428,428,428
BEGIN DESCRIPTION:
Mapping XS ff225b65
END DESCRIPTION:
XS GIS Cut Line= 2
      2861275.54     10174395.96      2860759.11     10174093.48
#Sta/Elev= 30
  4753.1 1073.63  4812.4 1070.56  4834.1  1068.1  4865.3 1063.33  4915.2  1058.4
  4951.2  1056.5  4988.4 1056.51  5004.1  1054.4  5007.9 1052.18  5008.1 1051.68
  5011.6 1051.68  5011.9 1052.18  5013.2 1052.18  5019.5  1052.2  5025.6 1054.55
  5031.4 1055.37  5041.3 1056.25    5047 1056.21  5062.7 1057.77  5068.5 1057.48
  5077.4 1058.13  5105.7 1058.45  5112.2 1059.55  5135.4 1059.35  5148.7 1060.32
  5185.8 1061.43  5201.5 1062.44  5207.3 1062.23  5255.9 1064.63  5351.6 1069.46
#Mann= 5 ,-1 , 0
  4753.1     .05       0  5007.9     .05       0  5011.9     .05       0
  5013.2     .12       0  5255.9     .05       0
Bank Sta=5007.9,5011.9
XS Rating Curve= 0 ,0
Exp/Cntr=0.3,0.1

Type RM Length L Ch R = 1 ,10000   ,357,357,357
BEGIN DESCRIPTION:
Mapping XS dd12c0ef
END DESCRIPTION:
XS GIS Cut Line= 2
      2861338.43     10174279.42      2861057.86     10173526.28
#Sta/Elev= 30
  4561.5 1068.25  4653.6 1062.79    4675 1062.41  4699.9 1060.21  4724.9 1059.63
  4730.3 1058.63  4755.3 1057.21  4815.9 1055.79  4840.9 1053.97  4846.3 1054.41
  4865.4 1053.64  4877.7 1052.98  4931.9 1052.84  4981.9 1050.98  4993.1 1049.88
  4993.3 1049.38  4997.1 1049.88    5014 1050.73  5067.6 1054.81  5072.9 1055.89
  5097.9 1055.85  5133.8 1057.69  5163.9 1058.02  5213.9 1060.81  5219.2 1060.47
  5238.9 1061.68  5244.2 1061.08  5291.8 1064.13  5321.8 1065.64  5365.2 1067.61
#Mann= 8 ,-1 , 0
  4561.5     .05       0  4865.4     .12       0  4993.1     .07       0
  4997.1     .12       0    5014     .05       0  5163.9     .12       0
  5291.8     .05       0  5321.8     .12       0
Bank Sta=4993.1,4997.1
XS Rating Curve= 0 ,0
Exp/Cntr=0.3,0.1

Type RM Length L Ch R = 1 ,9643    ,186,186,186
BEGIN DESCRIPTION:
SOUTH PRONG CREEK 21.0
END DESCRIPTION:
XS GIS Cut Line= 3
      2861490.14     10174175.79      2861443.88     10173772.45
      2861327.35     10173622.62
#Sta/Elev= 30
  4805.7 1065.92  4809.9 1065.89  4828.5 1064.09  4868.8 1062.05  4886.3 1059.49
    4899 1060.19  4929.2 1056.21  4939.3 1056.07  4975.5 1052.17  5009.7 1050.08
  5027.8 1046.22  5028.1 1045.72  5031.8 1046.22  5039.9 1048.49    5050 1049.28
  5059.6 1049.92  5064.6 1048.91  5080.4  1049.5  5130.5 1050.86  5154.9 1053.04
  5179.8 1055.82  5214.3  1058.8  5223.5 1060.91    5246 1062.47  5260.5  1064.7
  5266.8  1066.9  5274.2 1068.07  5322.1 1071.25  5351.9 1073.66  5401.5 1073.73
#Mann= 8 ,-1 , 0
  4805.7     .12       0  4809.9     .05       0  5027.8     .05       0
  5031.8     .05       0  5080.4     .12       0  5154.9     .05       0
  5179.8     .12       0  5322.1     .05       0
Bank Sta=5027.8,5031.8
XS Rating Curve= 0 ,0
Exp/Cntr=0.3,0.1

Type RM Length L Ch R = 1 ,9457    ,483,483,483
BEGIN DESCRIPTION:
SOUTH PRONG CREEK 20.0
END DESCRIPTION:
XS GIS Cut Line= 3
      2861706.62     10174055.56      2861591.89      10173829.8
      2861371.42     10173587.27
#Sta/Elev= 30
  4804.2 1060.36  4842.8 1059.02  4859.4 1055.95  4919.1 1051.95  4931.8 1052.12
  4953.3 1049.95  4967.1 1049.17  4998.6 1047.93  5013.2 1044.92  5013.5 1044.42
  5017.2 1044.92  5020.8 1046.25  5037.5 1048.37  5089.1 1049.07    5123  1051.1
  5187.2 1056.68  5236.5 1062.05  5243.3  1063.6  5250.7 1063.29  5257.5  1064.7
  5264.9 1064.57  5271.7 1066.39  5279.1 1065.93  5285.8  1067.1  5293.3 1066.51
  5328.4 1070.88  5355.3  1072.4  5363.8  1073.4    5371 1072.74  5385.2  1073.2
#Mann= 7 ,-1 , 0
  4804.2     .05       0  4953.3     .12       0  4967.1     .05       0
  5013.2     .05       0  5017.2     .05       0  5089.1     .12       0
  5355.3     .05       0
Bank Sta=5013.2,5017.2
XS Rating Curve= 0 ,0
Exp/Cntr=0.3,0.1

Type RM Length L Ch R = 1 ,8974    ,319,319,319
BEGIN DESCRIPTION:
SOUTH PRONG CREEK 19.0
END DESCRIPTION:
XS GIS Cut Line= 3
      2861876.81     10173713.23      2861619.65     10173433.87
      2861525.26      10173383.9
#Sta/Elev= 30
  4670.3  1061.4  4685.1  1060.7  4692.5 1061.16  4699.3 1059.65  4706.7 1059.84
  4713.5 1058.78    4735 1057.44  4741.8  1055.6  4763.4 1054.02  4784.3 1051.49
  4798.5 1050.42  4805.9 1050.84  4812.7 1049.51    4820 1050.17  4826.9 1048.38
  4841.1 1046.22  4876.2 1043.07    4912 1042.41  4947.1 1044.15  4968.7 1044.15
  4987.6 1040.97  4987.9 1040.47  4991.6 1040.97  5010.6 1046.99    5039 1051.53
  5046.4 1053.38  5055.1 1053.54  5061.2 1054.89  5130.2 1059.92  5156.8 1060.51
#Mann= 4 ,-1 , 0
  4670.3     .12       0  4987.6     .07       0  4991.6     .12       0
  5130.2     .05       0
Bank Sta=4987.6,4991.6
XS Rating Curve= 0 ,0
Exp/Cntr=0.3,0.1

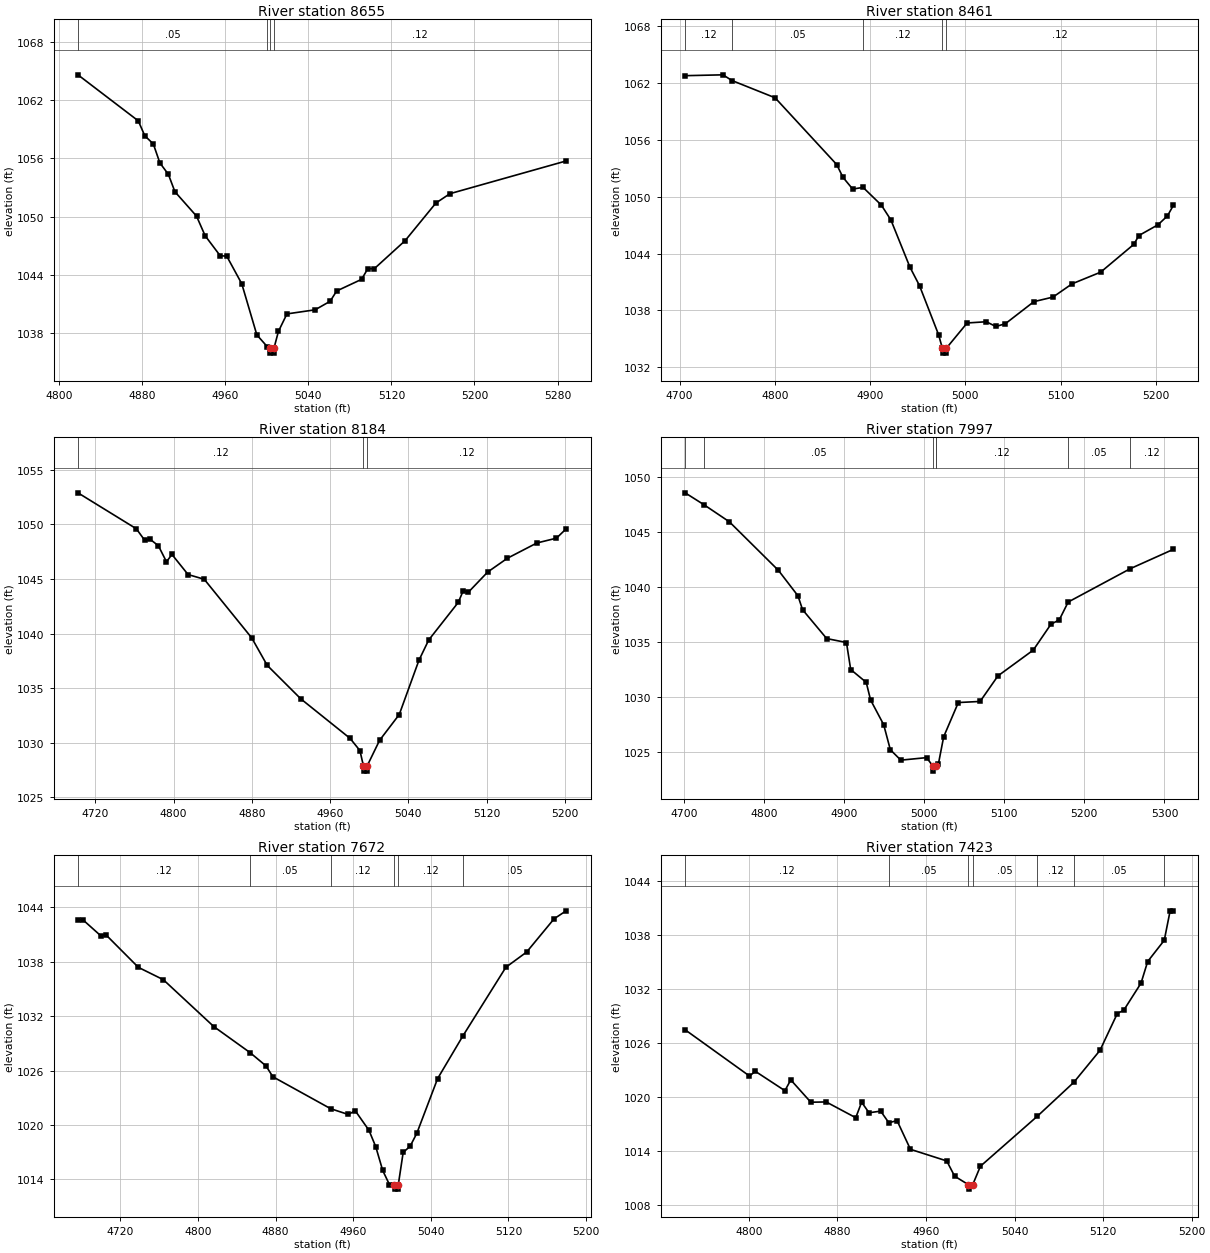
Type RM Length L Ch R = 1 ,8655    ,194,194,194
BEGIN DESCRIPTION:
SOUTH PRONG CREEK 18.0
END DESCRIPTION:
XS GIS Cut Line= 3
      2862026.71     10173613.37      2861873.12     10173413.52
      2861693.63     10173289.54
#Sta/Elev= 30
  4818.1 1064.59  4876.2 1059.85  4882.5 1058.31  4890.7 1057.47    4897 1055.52
  4905.2 1054.34  4911.5 1052.55  4932.3 1050.04  4940.6 1048.02  4955.1 1045.96
  4961.4 1045.92  4975.9 1043.07  4990.4 1037.81  5000.3 1036.61  5002.9 1036.43
  5003.2 1035.93  5006.7 1035.93  5006.9 1036.43  5011.2 1038.17  5019.4 1039.97
  5046.5 1040.39    5061 1041.27  5067.3 1042.33  5091.3 1043.53  5097.3 1044.63
  5103.5 1044.62  5133.2 1047.51  5162.9 1051.39  5176.4 1052.35  5288.3 1055.72
#Mann= 4 ,-1 , 0
  4818.1     .05       0  5000.3     .12       0  5002.9     .05       0
  5006.9     .12       0
Bank Sta=5002.9,5006.9
XS Rating Curve= 0 ,0
Exp/Cntr=0.3,0.1

Type RM Length L Ch R = 1 ,8461    ,277,277,277
BEGIN DESCRIPTION:
Mapping XS e7dcffdb
END DESCRIPTION:
XS GIS Cut Line= 3
      2862318.96     10173345.06      2862137.69     10173313.61
      2861809.49      10173330.2
#Sta/Elev= 30
  4705.8 1062.76  4745.5 1062.85  4754.9 1062.25  4800.2 1060.43  4864.9 1053.39
  4871.5 1052.04  4881.7  1050.8  4892.6 1050.98  4911.8 1049.11  4921.8 1047.55
  4941.8 1042.57  4951.9 1040.61  4971.9 1035.44  4975.9    1034  4976.2  1033.5
  4979.7  1033.5  4979.9    1034  5001.9 1036.68    5022 1036.81    5032 1036.31
    5042  1036.6    5072 1038.93    5092 1039.41  5112.1 1040.81  5142.1 1042.04
    5177 1044.98  5182.2  1045.9  5202.2 1047.03  5212.2 1047.97  5218.4 1049.08
#Mann= 5 ,-1 , 0
  4705.8     .12       0  4754.9     .05       0  4892.6     .12       0
  4975.9     .07       0  4979.9     .12       0
Bank Sta=4975.9,4979.9
XS Rating Curve= 0 ,0
Exp/Cntr=0.3,0.1

Type RM Length L Ch R = 1 ,8184    ,187,187,187
BEGIN DESCRIPTION:
Mapping XS 4b9a61cf
END DESCRIPTION:
XS GIS Cut Line= 3
      2862148.76     10173150.78      2862034.08     10173091.59
      2861665.89      10173128.6
#Sta/Elev= 30
  4702.2 1052.88  4761.9 1049.59  4770.5 1048.53  4776.1 1048.62  4784.4 1048.04
  4792.7 1046.57  4798.3 1047.24  4814.8  1045.4  4831.3 1044.97  4879.9  1039.6
  4895.7 1037.09  4930.1 1034.02  4980.4 1030.41  4990.5 1029.29    4994 1027.91
  4994.2 1027.41  4997.7 1027.41    4998 1027.91  5010.6 1030.23  5030.7 1032.59
  5050.8 1037.55  5060.8 1039.41    5091 1042.85  5096.2 1043.94  5101.2 1043.77
  5121.1 1045.63  5141.2 1046.89  5171.4 1048.29  5191.4 1048.73  5201.3 1049.58
#Mann= 3 ,-1 , 0
  4702.2     .12       0    4994     .07       0    4998     .12       0
Bank Sta=4994,4998
XS Rating Curve= 0 ,0
Exp/Cntr=0.3,0.1

Type RM Length L Ch R = 1 ,7997    ,325,325,325
BEGIN DESCRIPTION:
SOUTH PRONG CREEK 17.0
END DESCRIPTION:
XS GIS Cut Line= 3
      2862167.27     10173030.53      2861823.16     10172899.18
      2861609.61     10173011.47
#Sta/Elev= 30
  4701.5 1048.58  4725.3 1047.48  4756.7 1045.94    4818 1041.51  4842.3  1039.2
  4848.1 1037.93  4878.2  1035.3  4902.9 1034.94  4908.2 1032.48  4927.6 1031.31
    4933 1029.71  4949.4 1027.45  4957.7 1025.17  4970.8 1024.22  5002.9 1024.45
  5010.5 1023.72  5010.7 1023.22  5014.5 1023.72  5014.6 1023.73  5017.8  1023.9
  5024.3 1026.35  5042.6 1029.47  5069.8 1029.57  5092.1  1031.9  5136.2 1034.25
  5158.2  1036.6  5168.7 1037.01  5179.8 1038.63  5257.4 1041.67  5311.1 1043.43
#Mann= 7 ,-1 , 0
  4701.5     .12       0  4725.3     .05       0  5010.5     .05       0
  5014.5     .05       0  5014.6     .12       0  5179.8     .05       0
  5257.4     .12       0
Bank Sta=5010.5,5014.5
XS Rating Curve= 0 ,0
Exp/Cntr=0.3,0.1

Type RM Length L Ch R = 1 ,7672    ,249,249,249
BEGIN DESCRIPTION:
Mapping XS 531e0385
END DESCRIPTION:
XS GIS Cut Line= 3
      2862207.99     10172917.68      2862165.44     10172769.67
      2861923.12      10172518.1
#Sta/Elev= 30
  4676.2 1042.65  4681.2 1042.65  4699.6 1040.89  4704.8 1041.01  4738.5 1037.39
  4764.2 1036.03  4816.3 1030.85  4853.5 1027.99    4870 1026.52  4877.2 1025.31
  4936.7 1021.79  4954.9 1021.15  4962.1 1021.56  4976.2 1019.41  4983.2  1017.6
  4990.4 1014.97  4997.3 1013.42  5002.5 1013.41  5002.8 1012.91  5006.3 1012.91
  5006.5 1013.41  5011.5 1016.96  5018.7 1017.65  5025.6 1019.08    5047 1025.11
    5073 1029.81  5117.4  1037.4  5138.8 1039.08  5167.1 1042.75  5179.5 1043.63
#Mann= 6 ,-1 , 0
  4676.2     .12       0  4853.5     .05       0  4936.7     .12       0
  5002.5     .07       0  5006.5     .12       0    5073     .05       0
Bank Sta=5002.5,5006.5
XS Rating Curve= 0 ,0
Exp/Cntr=0.3,0.1

Type RM Length L Ch R = 1 ,7423    ,221,221,221
BEGIN DESCRIPTION:
SOUTH PRONG CREEK 16.0
END DESCRIPTION:
XS GIS Cut Line= 3
      2862339.34     10172751.12      2862276.45      10172556.9
       2862155.7     10172353.14
#Sta/Elev= 30
  4742.4 1027.47  4800.5 1022.34  4805.8 1022.86  4832.5 1020.71  4837.8 1021.91
  4855.9 1019.43  4869.8 1019.46  4896.5 1017.71  4901.8 1019.43  4908.5 1018.26
    4919 1018.44  4926.4 1017.15  4933.8 1017.39  4945.9  1014.2  4978.7 1012.91
  4985.8 1011.22  4998.2 1010.28  4998.4 1009.78  5002.2 1010.28  5009.1 1012.32
  5060.6 1017.88  5093.5 1021.64  5117.1 1025.18  5132.8 1029.28  5138.6 1029.64
  5154.2 1032.65  5160.2 1035.05  5175.2 1037.41  5180.5 1040.68  5183.4 1040.68
#Mann= 7 ,-1 , 0
  4742.4     .12       0  4926.4     .05       0  4998.2     .05       0
  5002.2     .05       0  5060.6     .12       0  5093.5     .05       0
  5175.2     .12       0
Bank Sta=4998.2,5002.2
XS Rating Curve= 0 ,0
Exp/Cntr=0.3,0.1

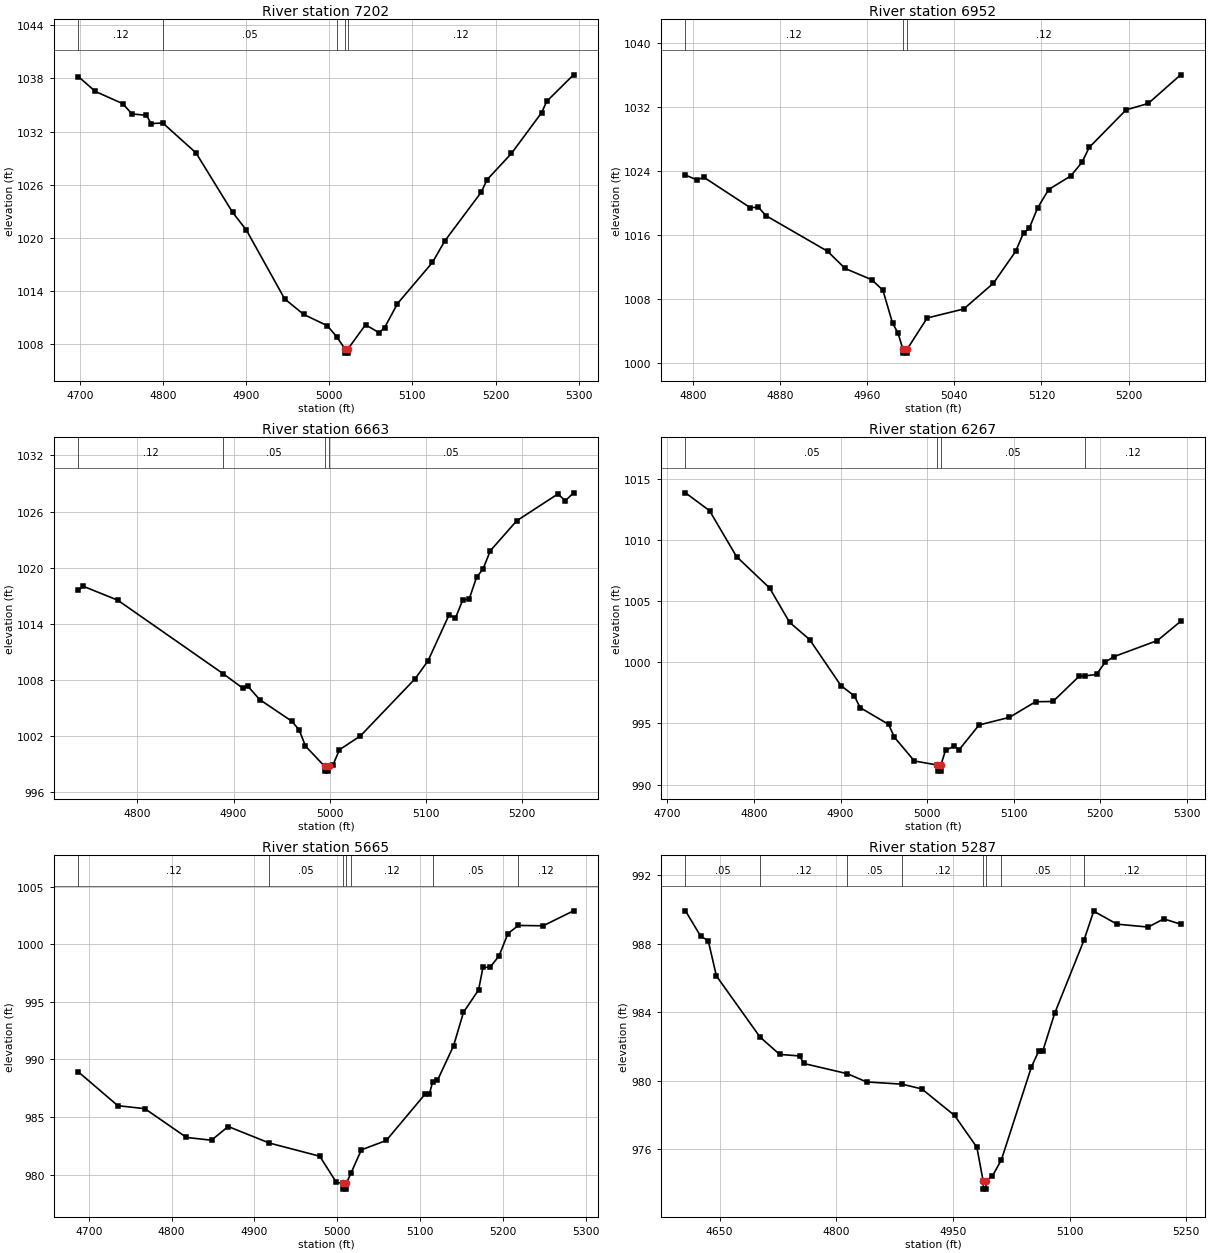
Type RM Length L Ch R = 1 ,7202    ,250,250,250
BEGIN DESCRIPTION:
Mapping XS 9d662e04
END DESCRIPTION:
XS GIS Cut Line= 3
      2862585.44      10172721.6      2862420.76     10172364.48
      2862254.21     10172249.75
#Sta/Elev= 30
  4698.2 1038.21  4718.6 1036.53  4751.6 1035.15  4762.7 1033.99  4780.2 1033.84
  4785.7  1032.9  4799.8 1032.97  4839.7  1029.6  4883.7  1022.9  4900.4 1020.88
  4946.3 1013.14  4969.3 1011.38  4997.7 1010.11  5008.8 1008.88  5018.7 1007.52
  5018.9 1007.02  5022.4 1007.02  5022.7 1007.52  5043.6 1010.22  5059.9 1009.32
  5066.6  1009.9    5082  1012.6  5124.1 1017.25    5139 1019.68  5182.6 1025.15
  5189.8 1026.58  5219.1 1029.54  5255.4 1034.14  5261.4  1035.4  5293.7  1038.4
#Mann= 5 ,-1 , 0
  4698.2     .12       0  4799.8     .05       0  5008.8     .12       0
  5018.7     .05       0  5022.7     .12       0
Bank Sta=5018.7,5022.7
XS Rating Curve= 0 ,0
Exp/Cntr=0.3,0.1

Type RM Length L Ch R = 1 ,6952    ,289,289,289
BEGIN DESCRIPTION:
SOUTH PRONG CREEK 15.0
END DESCRIPTION:
XS GIS Cut Line= 3
      2862731.58     10172351.53      2862629.83     10172246.07
      2862326.36     10172194.26
#Sta/Elev= 30
  4793.3 1023.47  4803.5 1022.89  4810.5 1023.17  4852.9 1019.39  4860.1 1019.48
  4867.1 1018.41  4923.7 1013.96  4939.8 1011.81  4964.3  1010.4  4974.5 1009.09
  4983.3    1005  4988.4 1003.73  4992.8 1001.74    4993 1001.24  4996.5 1001.24
  4996.8 1001.74  5015.1 1005.63  5048.6 1006.75  5075.9 1009.97  5096.2 1013.93
  5103.6 1016.27  5108.7 1016.81  5116.5 1019.39  5126.6 1021.67  5146.9 1023.37
  5157.1 1025.06  5163.8 1026.93  5197.7 1031.62  5217.9 1032.41  5247.7 1035.99
#Mann= 3 ,-1 , 0
  4793.3     .12       0  4992.8     .07       0  4996.8     .12       0
Bank Sta=4992.8,4996.8
XS Rating Curve= 0 ,0
Exp/Cntr=0.3,0.1

Type RM Length L Ch R = 1 ,6663    ,396,396,396
BEGIN DESCRIPTION:
SOUTH PRONG CREEK 14.0
END DESCRIPTION:
XS GIS Cut Line= 3
      2862761.19     10172223.88      2862738.99     10172035.16
      2862528.47     10171787.71
#Sta/Elev= 30
  4738.6 1017.58  4743.7 1018.02  4779.6 1016.53  4889.3 1008.67  4909.8 1007.12
  4914.8 1007.36  4927.1 1005.92  4960.5 1003.61  4968.2 1002.68  4974.8 1000.95
  4994.8  998.77    4995  998.27  4998.5  998.27  4998.8  998.77  5003.3  998.91
  5010.1 1000.55  5031.9 1002.03  5088.9 1008.15  5102.2 1010.05  5124.2 1014.98
  5130.7 1014.61  5138.4 1016.57    5145 1016.64  5152.7 1018.99  5159.3 1019.83
    5167 1021.81  5194.4 1025.01  5237.3 1027.88    5245 1027.15  5253.5    1028
#Mann= 4 ,-1 , 0
  4738.6     .12       0  4889.3     .05       0  4994.8     .05       0
  4998.8     .05       0
Bank Sta=4994.8,4998.8
XS Rating Curve= 0 ,0
Exp/Cntr=0.3,0.1

Type RM Length L Ch R = 1 ,6267    ,602,602,602
BEGIN DESCRIPTION:
SOUTH PRONG CREEK 13.0
END DESCRIPTION:
XS GIS Cut Line= 3
      2862840.73     10172236.85      2862981.36       10171926.
      2863005.23     10171696.42
#Sta/Elev= 30
  4720.8 1013.88  4748.6 1012.42  4779.8 1008.66    4818 1006.09  4841.1 1003.28
  4864.2 1001.87  4900.5  998.09  4915.9  997.26  4922.5   996.3  4955.4  994.93
  4962.1  993.88  4985.2  991.93  5011.8   991.6    5012   991.1  5015.5   991.1
  5015.8   991.6  5021.2   992.8  5031.4  993.16  5036.9  992.85    5060  994.88
    5095   995.5  5125.2  996.78  5145.3   996.8  5175.5  998.86  5182.5   998.9
  5195.6  999.01  5205.6 1000.02  5215.7 1000.47    5266 1001.79  5292.8 1003.36
#Mann= 4 ,-1 , 0
  4720.8     .05       0  5011.8     .05       0  5015.8     .05       0
  5182.5     .12       0
Bank Sta=5011.8,5015.8
XS Rating Curve= 0 ,0
Exp/Cntr=0.3,0.1

Type RM Length L Ch R = 1 ,5665    ,378,378,378
BEGIN DESCRIPTION:
SOUTH PRONG CREEK 12.0
END DESCRIPTION:
XS GIS Cut Line= 3
      2863455.69      10172253.1      2863497.55     10171835.34
      2863560.44     10171668.87
#Sta/Elev= 30
  4687.3  988.92    4735  985.98  4767.7  985.72  4817.9  983.22  4848.1  982.98
  4868.2  984.17  4918.1  982.73  4978.7  981.59  4998.8  979.32  5006.9  979.23
  5007.1  978.73  5010.6  978.73  5010.9  979.23  5016.5  980.13    5029  982.14
  5059.1  982.96  5105.8  986.97    5111  986.97  5115.2  988.08  5120.8  988.17
  5140.3  991.18  5152.3   994.1  5170.5  996.04  5175.8     998  5184.4  998.01
  5195.1  998.98    5206 1000.94  5218.6 1001.64  5248.5 1001.61  5285.1 1002.91
#Mann= 7 ,-1 , 0
  4687.3     .12       0  4918.1     .05       0  5006.9     .05       0
  5010.9     .05       0  5016.5     .12       0  5115.2     .05       0
  5218.6     .12       0
Bank Sta=5006.9,5010.9
XS Rating Curve= 0 ,0
Exp/Cntr=0.3,0.1

Type RM Length L Ch R = 1 ,5287    ,263,263,263
BEGIN DESCRIPTION:
SOUTH PRONG CREEK 11.0
END DESCRIPTION:
XS GIS Cut Line= 3
      2863804.67     10172342.28      2863865.73     10172001.85
      2863852.78      10171711.4
#Sta/Elev= 30
  4606.1  989.93  4625.6  988.45  4635.4  988.18  4645.9  986.12  4701.9  982.55
  4727.2  981.53    4753  981.44  4758.1     981  4814.4   980.4  4838.9  979.92
  4884.5  979.79    4910  979.51    4952  977.96  4980.7   976.1  4988.7  974.15
    4989  973.65  4992.5  973.65  4992.7  974.15  5000.8  974.42  5012.3  975.37
  5050.8  980.79  5060.5  981.75  5065.5  981.73  5080.8  983.94  5118.4  988.21
  5130.9  989.91  5160.9  989.15    5201  988.98    5221  989.46  5242.7  989.15
#Mann= 8 ,-1 , 0
  4606.1     .05       0  4701.9     .12       0  4814.4     .05       0
  4884.5     .12       0  4988.7     .07       0  4992.7     .12       0
  5012.3     .05       0  5118.4     .12       0
Bank Sta=4988.7,4992.7
XS Rating Curve= 0 ,0
Exp/Cntr=0.3,0.1