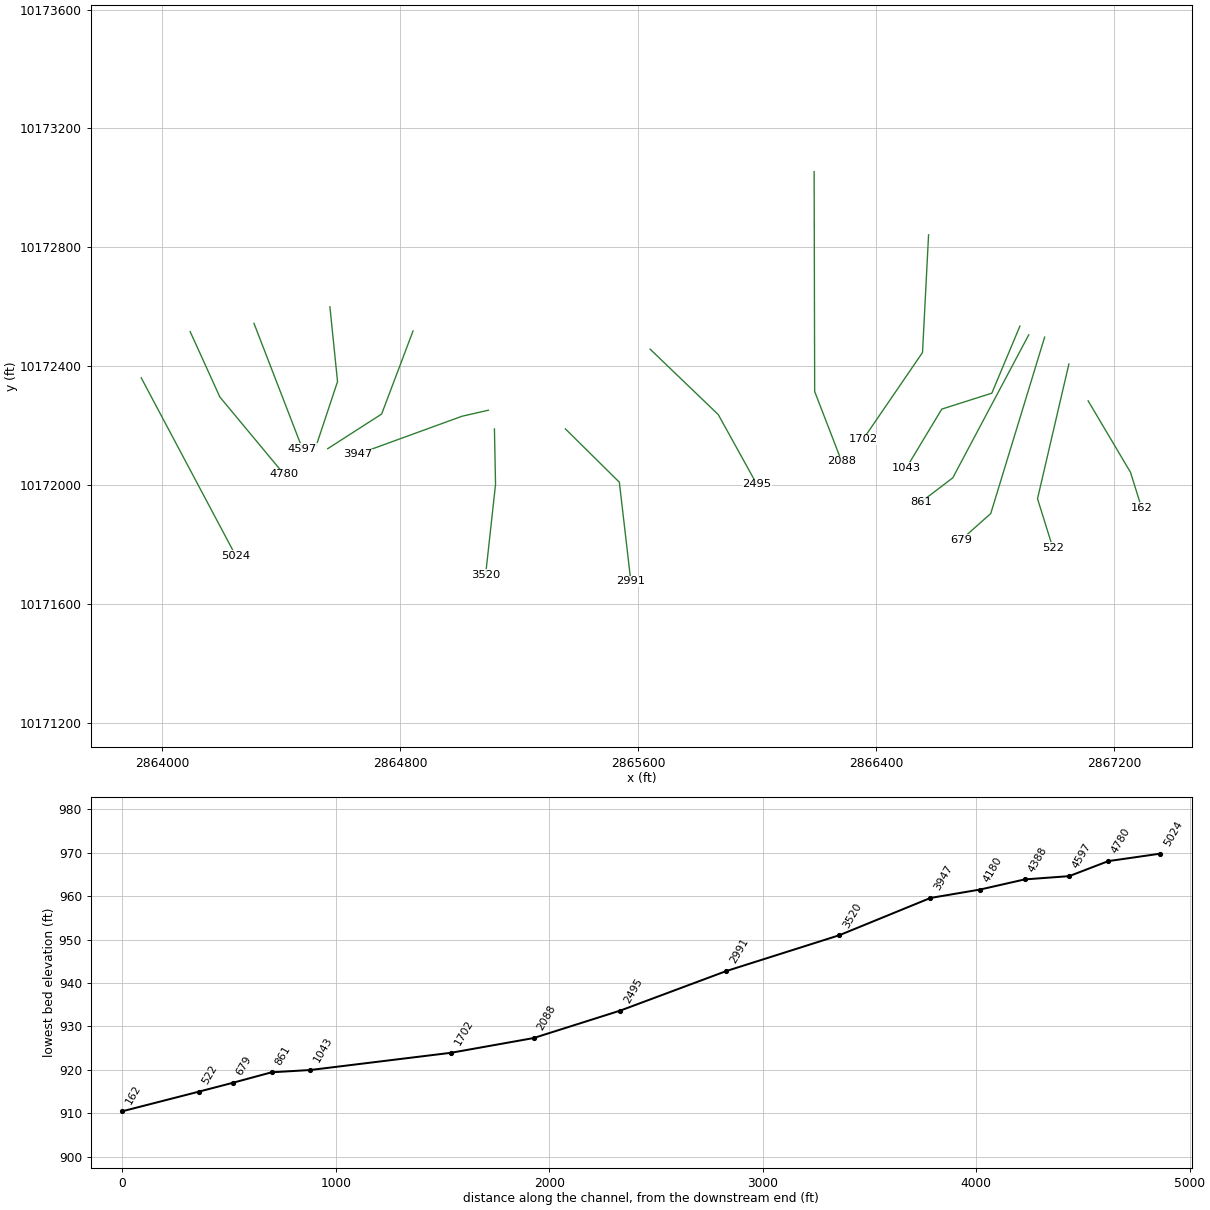
HEC-RAS study SOUTH PRONG CREEK.prj: SOUTH PRONG CREEK Base Level Engineering

--- SOUTH PRONG CREEK.g01 (geometry) --- (continued)

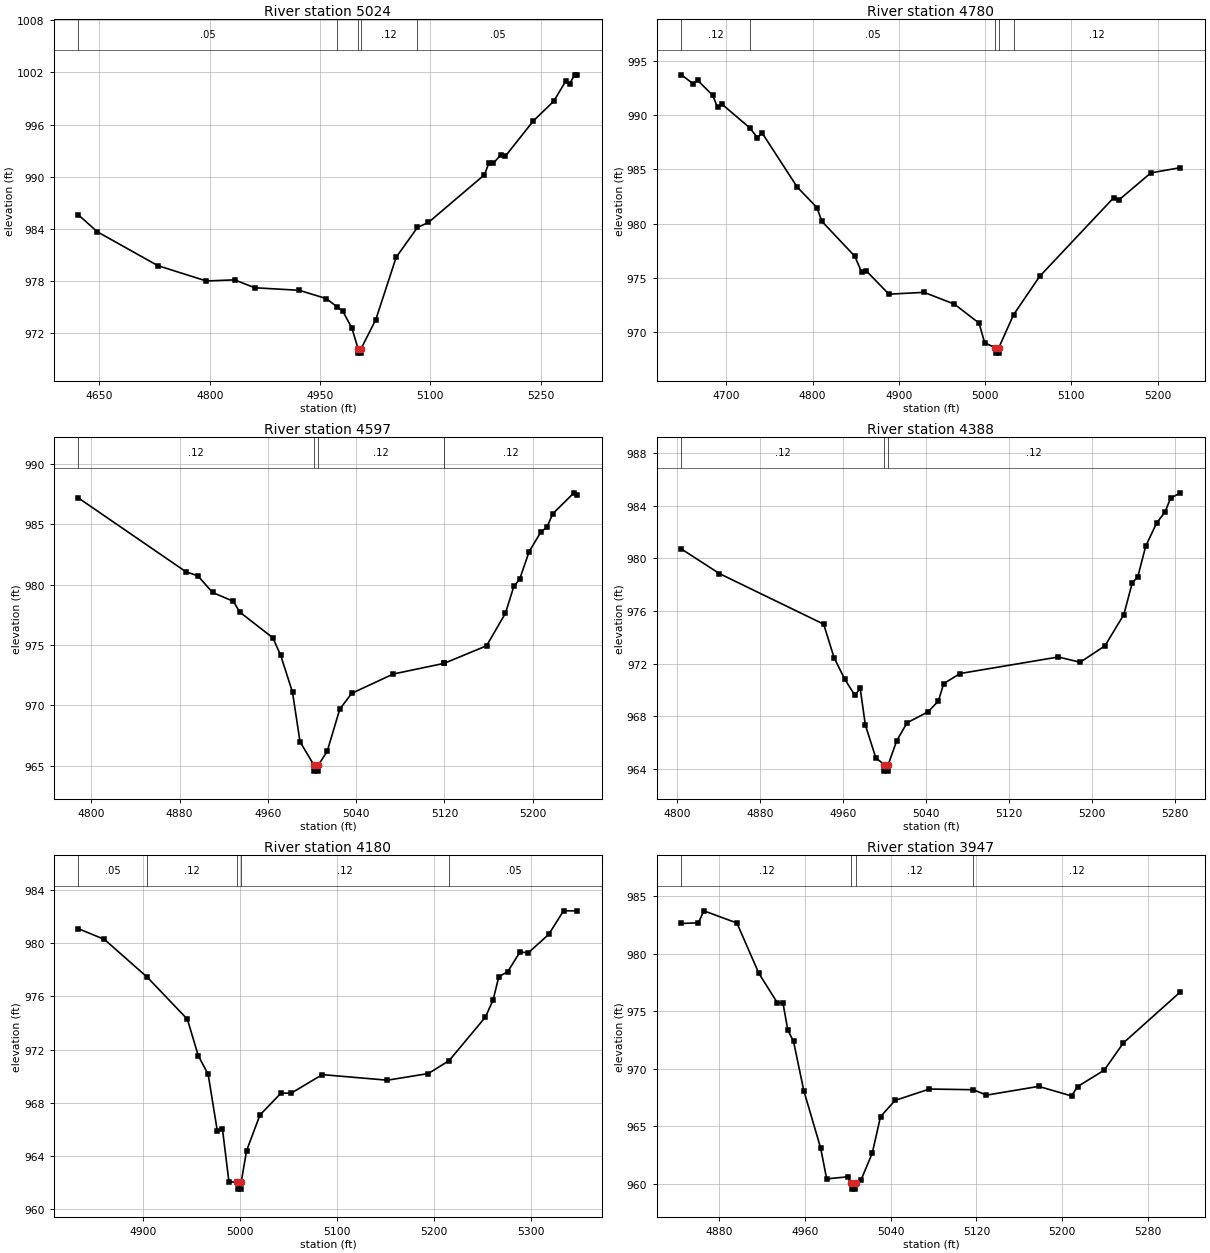
Type RM Length L Ch R = 1 ,5024    ,244,244,244
BEGIN DESCRIPTION:
Mapping XS 4eade6ca
END DESCRIPTION:
XS GIS Cut Line= 2
      2863928.64     10172360.77      2864246.87     10171761.31
#Sta/Elev= 30
  4621.5  985.61  4647.2  983.68  4729.5  979.79  4795.4  978.03  4833.7  978.16
  4861.4  977.25  4921.7  976.96  4958.5  976.01  4973.7  975.02  4981.1  974.54
  4993.3  972.63  5001.8  970.24    5002  969.74  5005.5  969.74  5005.8  970.24
  5025.9   973.6  5053.6  980.76  5082.5  984.18  5097.5  984.76  5173.6  990.23
  5179.8  991.61  5185.5  991.54  5196.1  992.54  5201.8  992.34  5240.1  996.42
  5267.8  998.68  5284.1 1000.98  5289.7 1000.71  5296.3 1001.72  5300.2 1001.72
#Mann= 5 ,-1 , 0
  4621.5     .05       0  4973.7     .12       0  5001.8     .07       0
  5005.8     .12       0  5082.5     .05       0
Bank Sta=5001.8,5005.8
XS Rating Curve= 0 ,0
Exp/Cntr=0.3,0.1

Type RM Length L Ch R = 1 ,4780    ,183,183,183
BEGIN DESCRIPTION:
SOUTH PRONG CREEK 10.0
END DESCRIPTION:
XS GIS Cut Line= 3
       2864093.3     10172516.19       2864193.2     10172296.03
      2864408.42     10172036.66
#Sta/Elev= 30
  4647.8  993.75  4661.2  992.93  4666.7  993.23  4684.1  991.85  4689.7  990.73
  4695.2  991.01  4726.8  988.86  4735.9  987.95  4741.4  988.37  4782.1  983.37
  4804.9  981.48  4810.6  980.21  4848.8  976.98  4856.8  975.51  4862.3  975.62
  4888.4  973.47  4929.2  973.64  4964.4  972.55    4993  970.79  4999.5  968.97
  5011.9  968.52  5012.1  968.02  5015.6  968.02  5015.9  968.52    5033  971.57
  5063.3  975.12  5149.3   982.4  5155.8  982.22  5192.2  984.68  5226.6  985.17
#Mann= 5 ,-1 , 0
  4647.8     .12       0  4726.8     .05       0  5011.9     .03       0
  5015.9     .05       0    5033     .12       0
Bank Sta=5011.9,5015.9
XS Rating Curve= 0 ,0
Exp/Cntr=0.3,0.1

Type RM Length L Ch R = 1 ,4597    ,209,209,209
BEGIN DESCRIPTION:
Mapping XS 174a07a6
END DESCRIPTION:
XS GIS Cut Line= 2
       2864307.9     10172543.98      2864470.69      10172122.2
#Sta/Elev= 30
  4788.4  987.15  4885.8  981.05  4896.5  980.72  4909.9  979.34  4928.7  978.61
  4934.5  977.72  4964.5  975.59  4971.6  974.14  4982.3  971.09  4989.1     967
  5001.7  965.07    5002  964.57  5005.5  964.57  5005.7  965.07  5013.7   966.2
  5025.1  969.69  5035.9     971  5073.6   972.6  5119.1  973.47  5119.6  973.48
  5158.1  974.93  5175.2  977.62  5182.8  979.84  5188.1  980.44  5196.6   982.7
  5207.4  984.36  5212.7  984.72  5218.1  985.85  5237.3  987.58  5240.5  987.42
#Mann= 5 ,-1 , 0
  4788.4     .12       0  5001.7     .07       0  5005.7     .12       0
  5119.1     .05       0  5119.6     .12       0
Bank Sta=5001.7,5005.7
XS Rating Curve= 0 ,0
Exp/Cntr=0.3,0.1

Type RM Length L Ch R = 1 ,4388    ,208,208,208
BEGIN DESCRIPTION:
SOUTH PRONG CREEK 9.0
END DESCRIPTION:
XS GIS Cut Line= 3
      2864563.23      10172599.5      2864588.86     10172347.93
      2864516.97     10172131.32
#Sta/Elev= 30
  4804.3  980.72  4840.9  978.85  4941.4     975  4951.4  972.46  4961.5  970.84
  4971.5  969.58  4976.6  970.12  4981.6  967.32  4991.7  964.82  4999.7  964.31
    5000  963.81  5003.5  963.81  5003.7  964.31  5011.8  966.12  5021.8  967.49
  5041.9  968.32    5052  969.14  5057.1  970.47  5072.8  971.24  5167.6   972.5
  5188.7   972.1  5212.6  973.35  5230.8  975.73    5239  978.17  5244.2  978.59
  5251.9  980.94  5262.4   982.7  5270.6  983.55  5275.9   984.6  5285.4     985
#Mann= 3 ,-1 , 0
  4804.3     .12       0  4999.7     .07       0  5003.7     .12       0
Bank Sta=4999.7,5003.7
XS Rating Curve= 0 ,0
Exp/Cntr=0.3,0.1

Type RM Length L Ch R = 1 ,4180    ,233,233,233
BEGIN DESCRIPTION:
Mapping XS 6d260fc1
END DESCRIPTION:
XS GIS Cut Line= 3
      2864842.62     10172518.08      2864737.15     10172238.67
      2864555.83     10172122.11
#Sta/Elev= 30
  4833.6  981.09  4860.3  980.29  4904.5  977.44  4945.8  974.28  4957.1  971.52
  4967.2  970.14  4976.6  965.89  4981.9  966.04  4988.6  962.06  4997.2  961.99
  4997.5  961.49    5001  961.49  5001.2  961.99  5006.8  964.39  5020.6  967.07
  5042.3  968.72  5052.7  968.71  5084.8  970.11  5151.8  969.69  5194.1  970.19
  5215.6  971.17  5252.9  974.44  5260.8  975.72  5266.7  977.48    5276  977.87
  5288.5  979.34  5297.1  979.28  5318.2  980.67  5333.4  982.44  5347.8  982.44
#Mann= 5 ,-1 , 0
  4833.6     .05       0  4904.5     .12       0  4997.2     .07       0
  5001.2     .12       0  5215.6     .05       0
Bank Sta=4997.2,5001.2
XS Rating Curve= 0 ,0
Exp/Cntr=0.3,0.1

Type RM Length L Ch R = 1 ,3947    ,427,427,427
BEGIN DESCRIPTION:
SOUTH PRONG CREEK 8.0
END DESCRIPTION:
XS GIS Cut Line= 3
      2865096.07     10172251.62      2865007.27     10172231.27
       2864655.7     10172103.12
#Sta/Elev= 30
    4845  982.64  4860.8   982.7  4865.9  983.74  4896.7  982.68  4917.2   978.3
  4934.4  975.75  4939.6  975.75  4944.2  973.37  4949.5  972.39  4959.1   968.1
  4974.8  963.12  4980.4  960.44    5000  960.62  5003.4  960.05  5003.6  959.55
  5007.1  959.55  5007.4  960.05  5012.3  960.32  5022.9  962.67  5030.6  965.85
  5044.2  967.26  5076.2  968.25  5117.2  968.19  5129.4  967.72  5178.1  968.48
  5208.7  967.65  5214.5  968.47  5239.2  969.89  5257.1  972.26  5310.3   976.7
#Mann= 4 ,-1 , 0
    4845     .12       0  5003.4     .07       0  5007.4     .12       0
  5117.2     .12       0
Bank Sta=5003.4,5007.4
XS Rating Curve= 0 ,0
Exp/Cntr=0.3,0.1

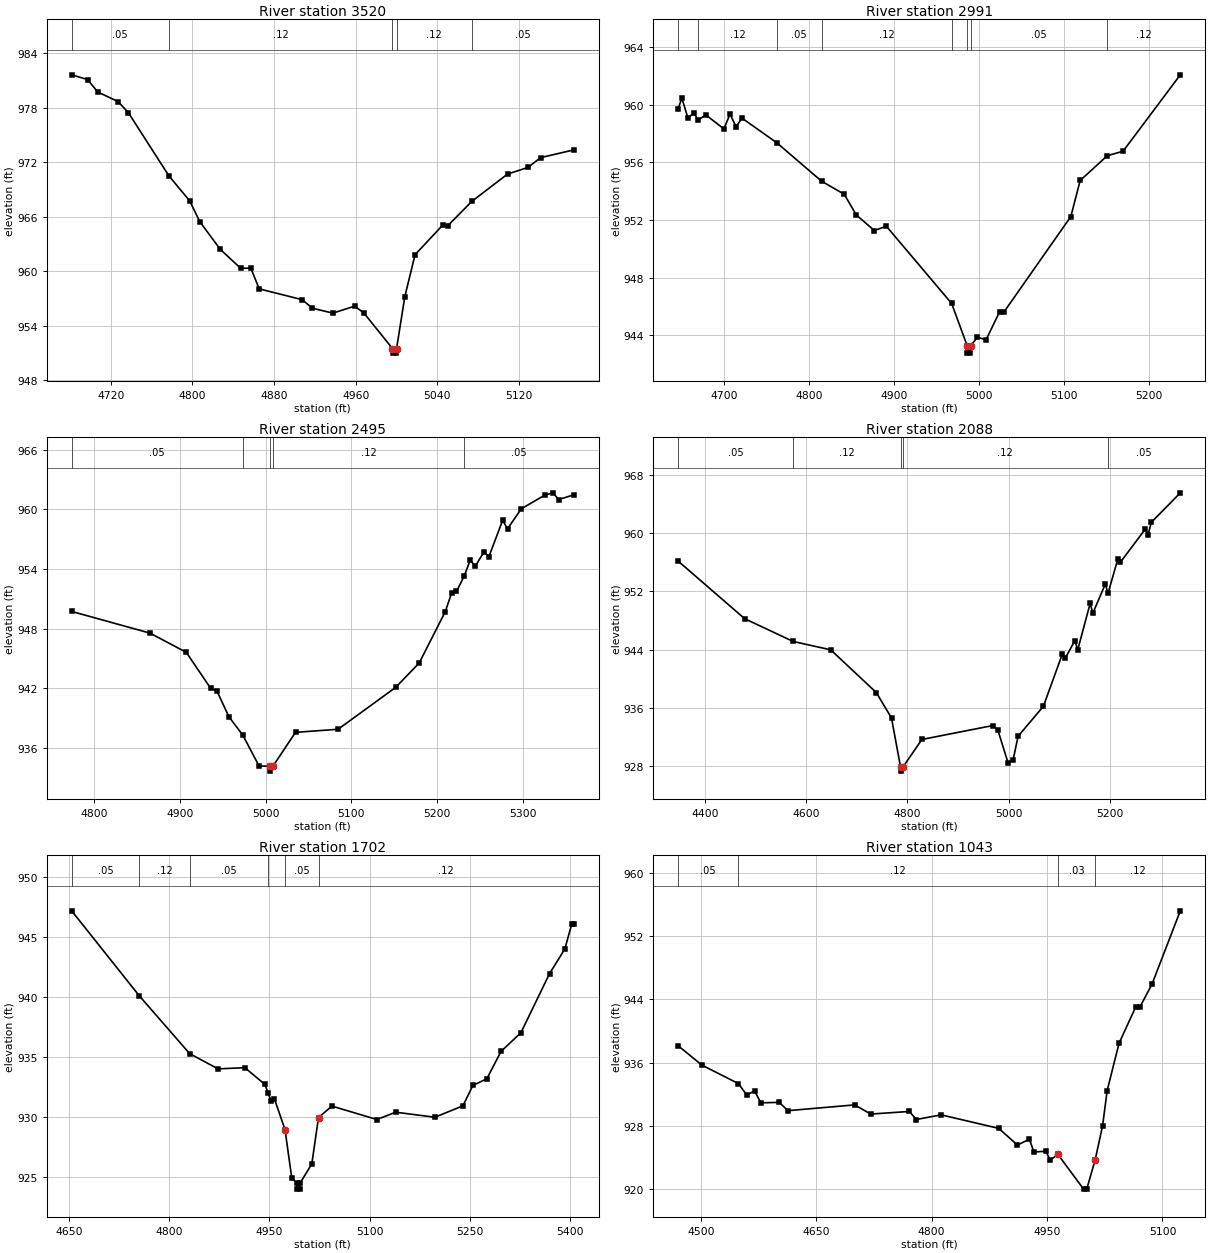
Type RM Length L Ch R = 1 ,3520    ,529,529,529
BEGIN DESCRIPTION:
SOUTH PRONG CREEK 7.0
END DESCRIPTION:
XS GIS Cut Line= 3
      2865116.43      10172188.7      2865120.13     10172001.85
      2865086.83     10171698.46
#Sta/Elev= 30
  4681.7   981.6  4697.3  981.08  4707.3  979.71  4727.3  978.65  4737.3  977.43
  4776.9   970.5  4797.3  967.74  4807.3  965.44  4827.3   962.4  4847.3  960.32
  4857.3  960.32  4865.5  958.05  4907.6  956.86  4917.6  955.92  4937.7  955.38
    4959  956.15  4967.9  955.42  4996.1  951.48  4996.3  950.98  4999.8  950.98
  5000.1  951.48  5008.2  957.21  5018.2  961.81  5045.1  965.04  5050.1  964.98
  5073.9  967.68  5108.8  970.68  5128.9  971.41  5141.2  972.49  5173.8  973.34
#Mann= 5 ,-1 , 0
  4681.7     .05       0  4776.9     .12       0  4996.1     .07       0
  5000.1     .12       0  5073.9     .05       0
Bank Sta=4996.1,5000.1
XS Rating Curve= 0 ,0
Exp/Cntr=0.3,0.1

Type RM Length L Ch R = 1 ,2991    ,496,496,496
BEGIN DESCRIPTION:
SOUTH PRONG CREEK 6.0
END DESCRIPTION:
XS GIS Cut Line= 3
      2865355.08     10172188.73      2865536.41     10172009.26
      2865575.05     10171676.22
#Sta/Elev= 30
  4646.3  959.73  4650.7  960.47  4657.8   959.1  4664.8  959.43  4669.9  958.96
    4679   959.3  4700.2  958.33  4707.3  959.37  4714.4  958.48  4721.4  959.08
  4762.3  957.37  4814.9   954.7  4841.6  953.79  4855.8  952.35    4877  951.27
  4891.1  951.57  4967.9   946.2  4986.2  943.25  4986.4  942.75  4989.9  942.75
  4990.2  943.25  4998.2  943.86  5008.3  943.67  5024.3  945.63  5029.4  945.61
    5108  952.24    5119  954.75  5150.9  956.47  5169.4  956.78  5236.7  962.09
#Mann= 8 ,-1 , 0
  4646.3     .05       0  4669.9     .12       0  4762.3     .05       0
  4814.9     .12       0  4967.9     .05       0  4986.2     .05       0
  4990.2     .05       0  5150.9     .12       0
Bank Sta=4986.2,4990.2
XS Rating Curve= 0 ,0
Exp/Cntr=0.3,0.1

Type RM Length L Ch R = 1 ,2495    ,407,407,407
BEGIN DESCRIPTION:
SOUTH PRONG CREEK 5.0
END DESCRIPTION:
XS GIS Cut Line= 3
      2865640.03     10172456.99      2865869.05     10172236.89
      2865998.96     10172001.84
#Sta/Elev= 30
  4773.5  949.73    4865  947.55  4907.4  945.61  4935.7     942    4943  941.75
  4957.1  939.13  4973.3  937.29  4992.3  934.18  5004.5  934.17  5004.7  933.67
  5008.5  934.17  5034.8  937.57  5084.5  937.88  5151.7  942.09  5179.2  944.55
  5209.7  949.72    5217  951.59  5222.7  951.74    5232  953.34  5238.8  954.92
  5244.5  954.26  5254.8  955.72  5260.5  955.22  5276.6   958.9  5282.3  958.04
  5298.3  960.05  5325.8  961.43  5335.4  961.66  5341.9  960.98  5359.7  961.46
#Mann= 5 ,-1 , 0
  4773.5     .05       0  4973.3     .12       0  5004.5     .07       0
  5008.5     .12       0    5232     .05       0
Bank Sta=5004.5,5008.5
XS Rating Curve= 0 ,0
Exp/Cntr=0.3,0.1

Type RM Length L Ch R = 1 ,2088    ,386,386,386
BEGIN DESCRIPTION:
SOUTH PRONG CREEK 4.0
END DESCRIPTION:
XS GIS Cut Line= 3
      2866191.37     10173054.59      2866193.22     10172314.53
      2866283.87     10172079.57
#Sta/Elev= 30
    4347  956.14  4478.5  948.24  4574.2  945.12  4648.5  943.97  4738.5  938.11
  4768.5  934.62  4786.5  927.84  4786.7  927.34  4790.5  927.84  4828.5  931.68
  4968.5  933.59  4978.5  932.98  4998.5  928.51  5008.5  928.82  5018.5  932.12
  5068.5  936.23  5106.2  943.45  5111.6  942.82  5130.8  945.24  5136.2  943.95
  5160.8  950.33  5166.2     949  5190.8  952.99  5196.1   951.7  5215.4   956.4
  5220.7  955.99    5270  960.55  5275.3  959.75  5281.5  961.44  5338.9   965.5
#Mann= 5 ,-1 , 0
    4347     .05       0  4574.2     .12       0  4786.5     .07       0
  4790.5     .12       0  5196.1     .05       0
Bank Sta=4786.5,4790.5
XS Rating Curve= 0 ,0
Exp/Cntr=0.3,0.1

Type RM Length L Ch R = 1 ,1702    ,659,659,659
BEGIN DESCRIPTION:
SOUTH PRONG CREEK 3.0
END DESCRIPTION:
XS GIS Cut Line= 3
       2866576.2     10172841.83      2866555.84     10172445.89
       2866355.7     10172153.13
#Sta/Elev= 30
  4654.4  947.15  4755.4  940.08  4830.9  935.25  4873.4  933.98  4913.5  934.08
  4943.5  932.68  4948.3  931.96  4952.5  931.33  4957.6   931.5  4973.5  928.92
  4983.6  924.89  4991.2  924.46  4991.5  923.96  4995.6  923.96    4996  924.46
  5013.6  926.06  5023.6  929.92  5043.6  930.88    5111  929.76    5139  930.37
  5197.6  929.95  5239.6   930.9  5254.5   932.6  5275.5  933.16  5296.5  935.43
  5326.3  936.99  5369.2  941.92    5392  943.97  5402.5  946.07  5405.5  946.07
#Mann= 6 ,-1 , 0
  4654.4     .05       0  4755.4     .12       0  4830.9     .05       0
  4948.3     .12       0  4973.5     .05       0  5023.6     .12       0
Bank Sta=4973.5,5023.6
XS Rating Curve= 0 ,0
Exp/Cntr=0.3,0.1

Type RM Length L Ch R = 1 ,1043    ,182,182,182
BEGIN DESCRIPTION:
Mapping XS bffe9772
END DESCRIPTION:
XS GIS Cut Line= 4
      2866883.33     10172534.72      2866788.96     10172308.98
       2866620.6     10172255.33      2866501.32     10172057.13
#Sta/Elev= 30
  4470.5  938.15  4501.3   935.7  4548.8  933.36  4559.8   931.9  4569.8  932.44
  4578.1  930.92  4601.9  930.98  4613.2  929.93  4699.9  930.66  4720.9   929.5
  4771.1  929.83  4780.1  928.81  4812.3   929.4  4887.2  927.69  4911.5  925.58
  4927.1  926.31  4932.9   924.7  4948.4  924.79  4954.3  923.66    4964  924.41
  4997.5     920  5001.6     920  5012.5  923.69  5022.2  928.02  5028.1  932.46
  5043.6  938.47    5065     943  5070.8  943.07  5086.3  945.91  5123.2  955.22
#Mann= 4 ,-1 , 0
  4470.5     .05       0  4548.8     .12       0    4964     .03       0
  5012.5     .12       0
Bank Sta=4964,5012.5
XS Rating Curve= 0 ,0
Exp/Cntr=0.3,0.1

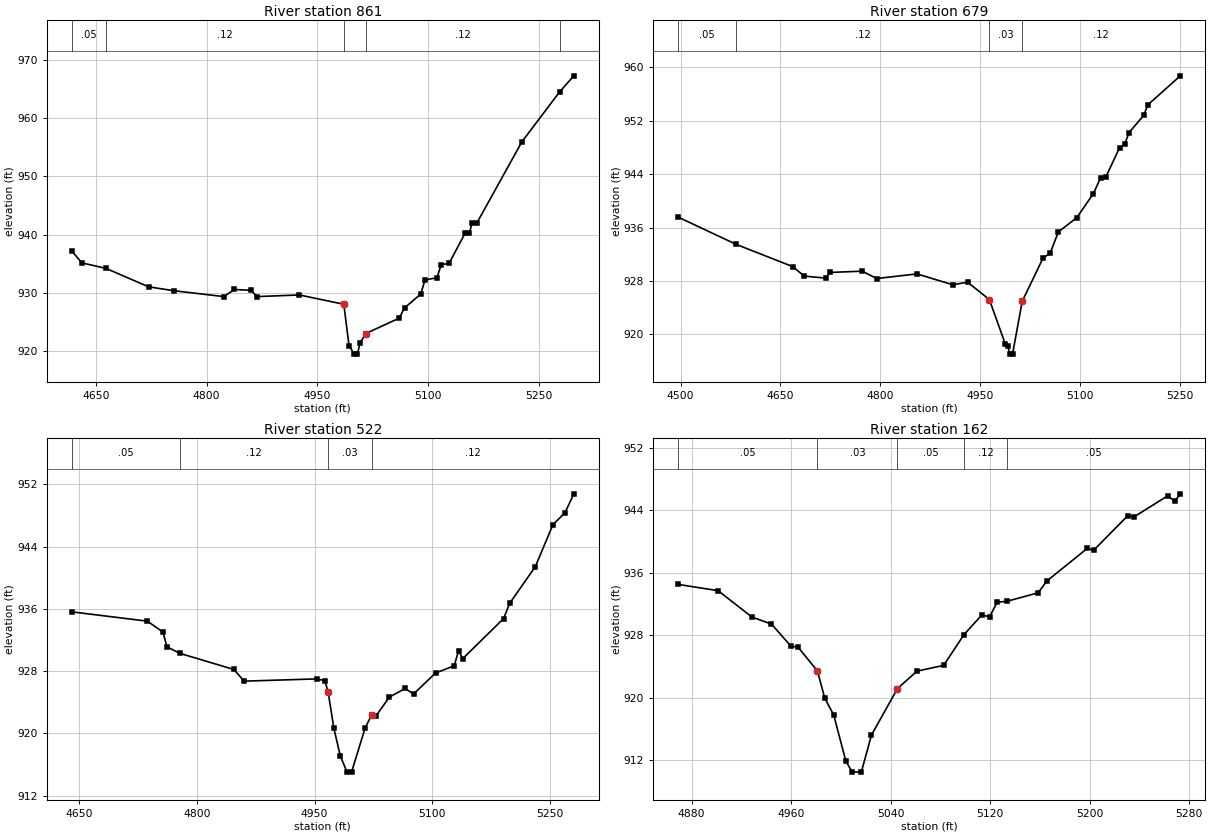
Type RM Length L Ch R = 1 ,861     ,182,182,182
BEGIN DESCRIPTION:
Mapping XS 7fbe93a1
END DESCRIPTION:
XS GIS Cut Line= 3
      2866912.94     10172505.13       2866657.6     10172024.06
      2866549.58     10171941.66
#Sta/Elev= 30
  4617.1  937.25  4630.7  935.16  4663.5  934.21  4721.3  931.04  4755.4  930.37
  4823.2  929.36  4837.7  930.58  4859.7  930.44  4868.5  929.36  4925.6  929.64
  4985.9  928.04    4993  920.91  5000.2  919.47  5004.3  919.47  5007.9  921.38
  5015.6     923  5060.9  925.65  5068.2  927.41  5090.2  929.81  5095.9  932.21
  5112.2  932.61  5117.8  934.84  5128.5  935.07  5150.5  940.31  5156.2  940.22
  5159.4  941.99  5166.1  941.99  5227.2  955.96  5278.5  964.57  5297.6   967.3
#Mann= 5 ,-1 , 0
  4617.1     .05       0  4663.5     .12       0  4985.9     .03       0
  5015.6     .12       0  5278.5     .05       0
Bank Sta=4985.9,5015.6
XS Rating Curve= 0 ,0
Exp/Cntr=0.3,0.1

Type RM Length L Ch R = 1 ,679     ,157,157,157
BEGIN DESCRIPTION:
SOUTH PRONG CREEK 2.0
END DESCRIPTION:
XS GIS Cut Line= 3
      2866966.57     10172497.68      2866785.26      10171903.8
      2866685.37       10171815.
#Sta/Elev= 30
  4496.2  937.57  4583.7  933.47  4668.3  930.16  4685.8  928.73  4718.6  928.43
  4723.8  929.28  4772.8  929.47  4794.7  928.37    4855  929.06  4908.8  927.44
  4931.1  927.82  4963.9  925.22 4987.77  918.58 4991.69  918.34  4994.4  917.05
 4998.72  917.06  5013.3  924.96  5044.7  931.47  5055.1  932.13  5067.6  935.36
  5095.2  937.47  5120.2  941.09  5131.2  943.49  5138.7  943.52  5159.6  947.97
  5167.1  948.47  5173.8  950.22  5195.6  952.78  5202.3   954.4  5250.8  958.72
#Mann= 4 ,-1 , 0
  4496.2     .05       0  4583.7     .12       0  4963.9     .03       0
  5013.3     .12       0
Bank Sta=4963.9,5013.3
XS Rating Curve= 0 ,0
Exp/Cntr=0.3,0.1

Type RM Length L Ch R = 1 ,522     ,360,360,360
BEGIN DESCRIPTION:
Mapping XS 2f1e93df
END DESCRIPTION:
XS GIS Cut Line= 3
      2867047.99     10172407.04      2866942.53     10171953.75
      2866994.19      10171787.7
#Sta/Elev= 30
  4640.8  935.62  4737.2  934.42    4757  933.02  4762.1  931.13  4778.5  930.29
  4847.3  928.22  4860.4  926.72  4952.8  927.01  4963.1  926.78 4967.22  925.39
 4974.59  920.68 4982.78  917.13 4991.38  915.04 4997.29   915.1  5014.5  920.74
  5022.8  922.39    5028  922.22  5045.3  924.68  5065.4  925.78  5076.1  925.07
    5104  927.76  5127.8  928.69  5133.4  930.64  5138.6   929.6  5190.7  934.76
  5198.4  936.71    5231  941.41  5253.5  946.81  5268.8  948.34  5280.1  950.77
#Mann= 4 ,-1 , 0
  4640.8     .05       0  4778.5     .12       0 4967.22     .03       0
  5022.8     .12       0
Bank Sta=4967.22,5022.8
XS Rating Curve= 0 ,0
Exp/Cntr=0.3,0.1

Type RM Length L Ch R = 1 ,162     ,0,0,0
BEGIN DESCRIPTION:
SOUTH PRONG CREEK 1.0
END DESCRIPTION:
XS GIS Cut Line= 3
      2867112.74     10172283.07       2867255.2     10172042.56
      2867292.21     10171924.14
#Sta/Elev= 30
  4869.2  934.51  4901.3  933.71  4928.6  930.33  4944.2  929.44  4959.8  926.63
  4965.6  926.48  4981.2  923.44    4987  919.99 4994.32  917.79    5004  911.91
 5009.01  910.55 5016.43  910.51 5024.59  915.25  5045.5   921.2  5061.2  923.42
  5082.6  924.16  5098.9  928.08  5113.2  930.59  5119.6  930.37  5125.5  932.22
  5133.7  932.36  5158.6  933.44  5165.5  934.94    5198  939.11  5203.2  938.88
  5230.5  943.28  5235.7  943.15  5262.9  945.86  5268.2  945.11  5272.8  946.09
#Mann= 5 ,-1 , 0
  4869.2     .05       0  4981.2     .03       0  5045.5     .05       0
  5098.9     .12       0  5133.7     .05       0
Bank Sta=4981.2,5045.5
XS Rating Curve= 0 ,0
Exp/Cntr=0.3,0.1

Chan Stop Cuts=-1
Use User Specified Reach Order=0
Composite Channel Slope=5