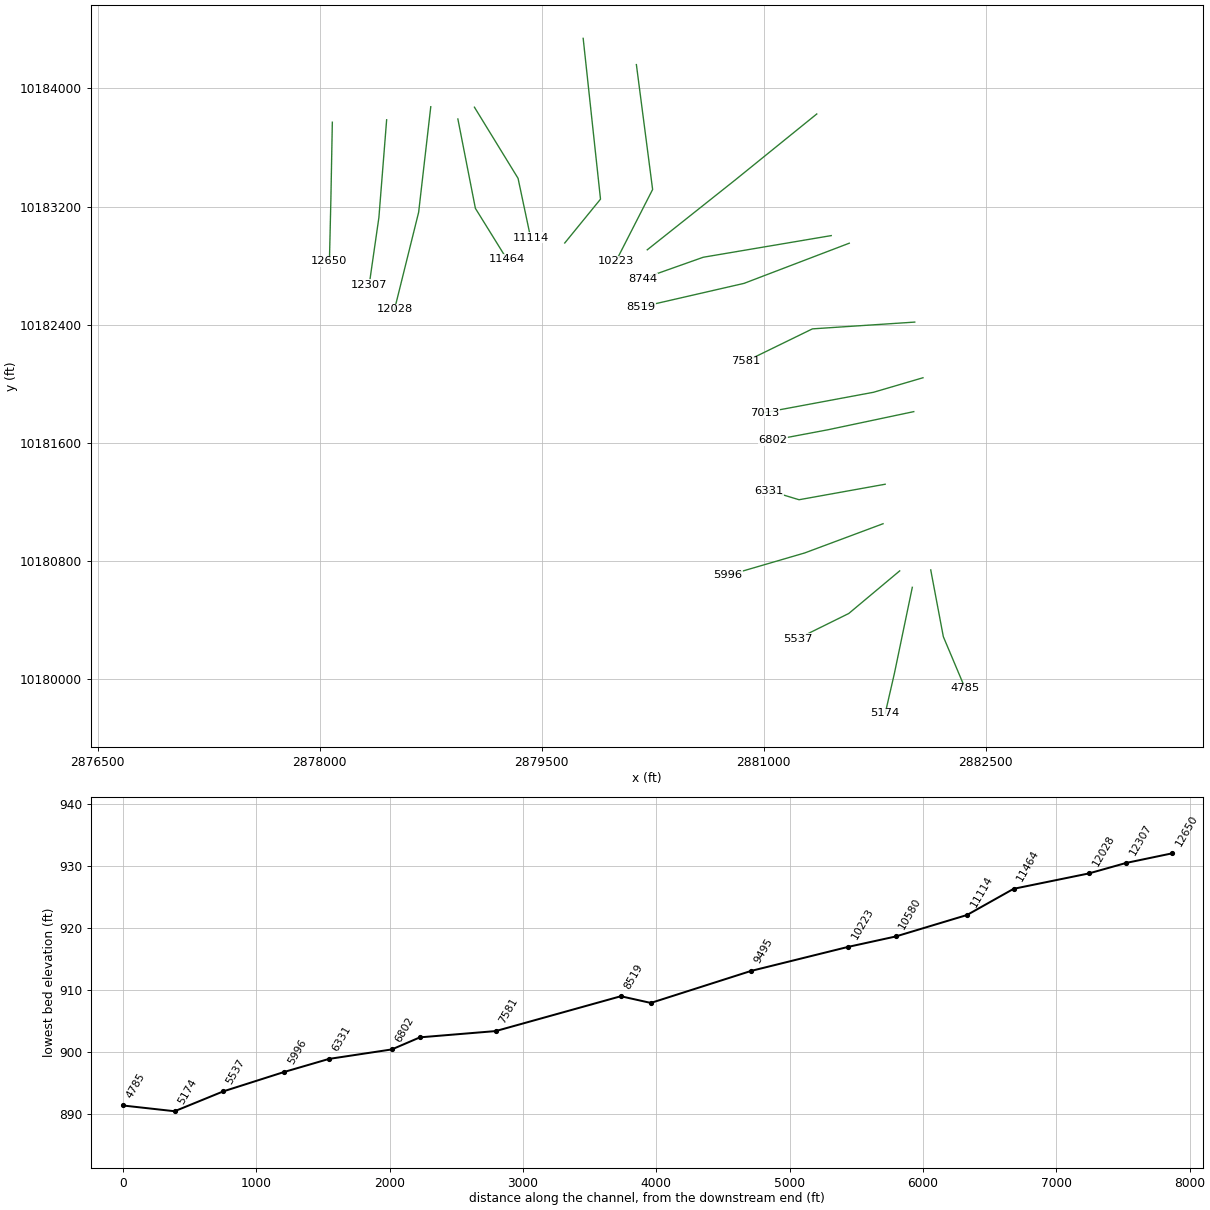
HEC-RAS study UPSHAW CREEK.prj: UPSHAW CREEK Base Level Engineering

--- UPSHAW CREEK.g01 (geometry) --- (continued)

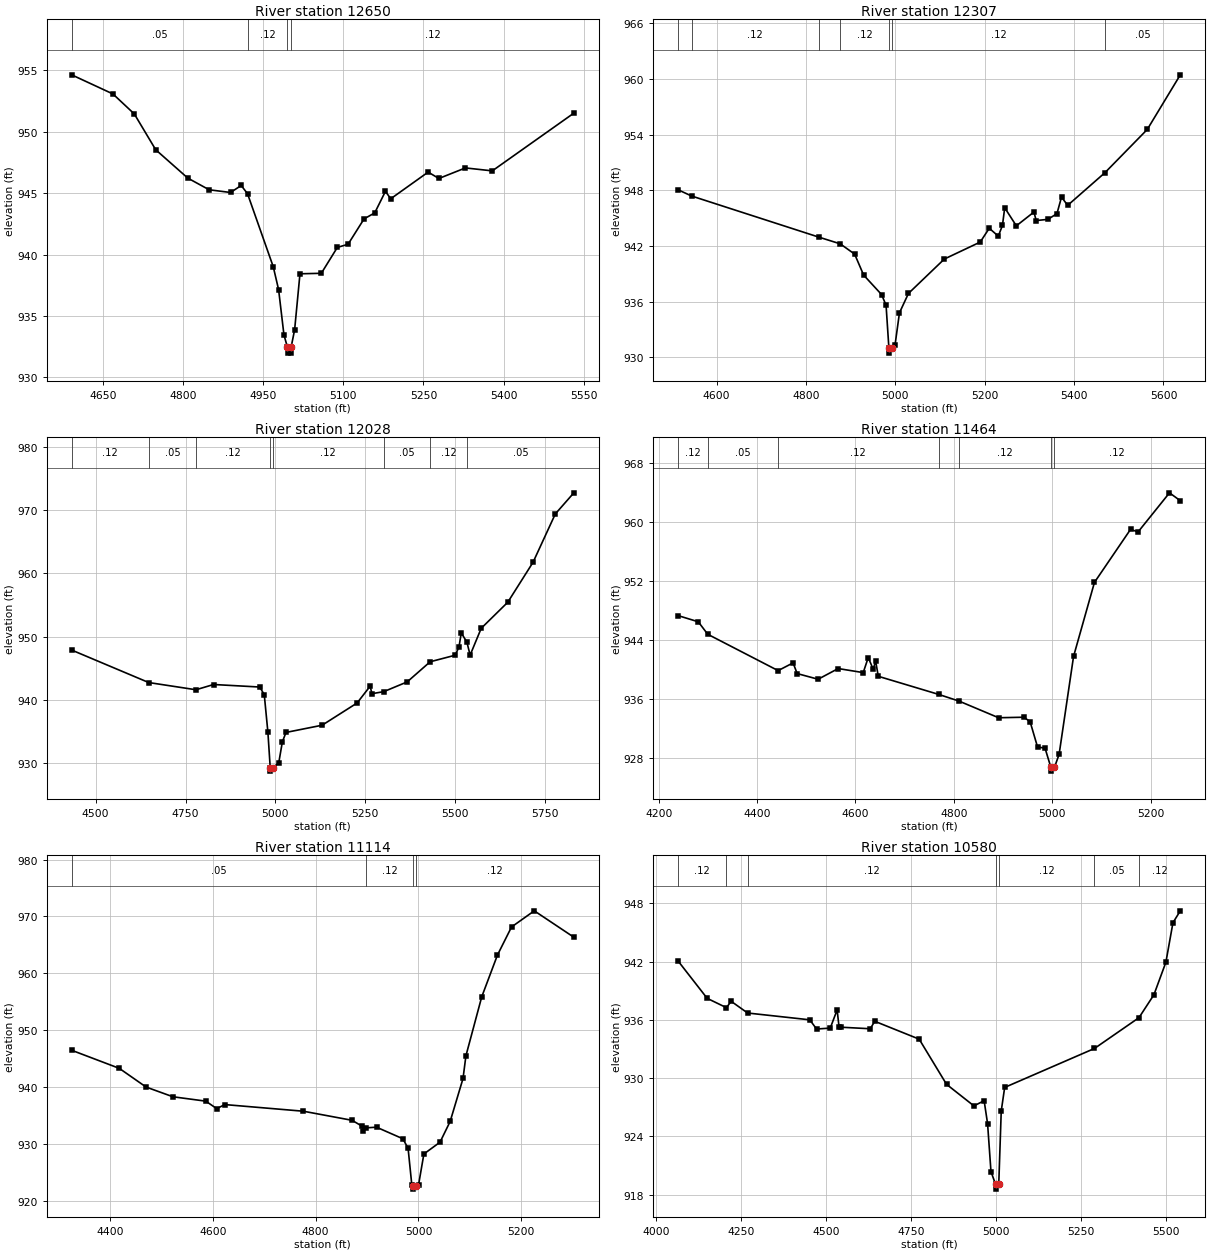
Type RM Length L Ch R = 1 ,12650   ,343,343,343
BEGIN DESCRIPTION:
UPSHAW CREEK 27.0
END DESCRIPTION:
XS GIS Cut Line= 3
      2878085.66     10183770.53      2878075.83     10183246.47
        2878066.     10182830.44
#Sta/Elev= 30
  4591.4  954.64  4668.8  953.08  4708.8  951.45  4748.8  948.54  4808.9  946.23
  4848.9  945.28  4888.9  945.06  4908.9  945.63  4920.7  944.96  4968.9  939.01
  4978.9  937.15  4988.9  933.47  4995.3  932.48  4995.8  931.98  5001.9  931.98
  5002.4  932.48  5008.9  933.88  5018.9  938.44  5058.9  938.48  5088.9  940.59
  5108.9  940.84  5138.9  942.91  5158.9   943.4  5178.9  945.15  5188.9  944.55
  5258.9  946.72    5279   946.2  5328.7  947.06    5379  946.82  5531.7  951.52
#Mann= 4 ,-1 , 0
  4591.4     .05       0  4920.7     .12       0  4995.3     .07       0
  5002.4     .12       0
Bank Sta=4995.3,5002.4
XS Rating Curve= 0 ,0
Exp/Cntr=0.3,0.1

Type RM Length L Ch R = 1 ,12307   ,279,279,279
BEGIN DESCRIPTION:
UPSHAW CREEK 26.0
END DESCRIPTION:
XS GIS Cut Line= 3
      2878452.53     10183786.91      2878400.12     10183125.27
      2878334.61     10182669.97
#Sta/Elev= 30
    4514  948.06    4544  947.39  4829.7  942.94  4876.7  942.23    4909  941.12
  4929.1  938.86  4969.2  936.76  4979.3  935.61  4985.7  930.94  4986.2  930.44
  4992.8  930.94  4999.3  931.29  5009.3  934.79  5029.4  936.88  5109.7  940.59
    5190  942.42  5210.2  943.91  5230.4  943.06  5239.7  944.21  5244.8  946.12
  5270.8  944.17  5310.2  945.66  5315.2  944.74  5341.5  944.87  5361.7  945.49
  5371.9  947.27  5385.7  946.38  5469.2  949.91  5563.8  954.57  5637.7  960.46
#Mann= 7 ,-1 , 0
    4514     .05       0    4544     .12       0  4829.7     .05       0
  4876.7     .12       0  4985.7     .07       0  4992.8     .12       0
  5469.2     .05       0
Bank Sta=4985.7,4992.8
XS Rating Curve= 0 ,0
Exp/Cntr=0.3,0.1

Type RM Length L Ch R = 1 ,12028   ,564,564,564
BEGIN DESCRIPTION:
UPSHAW CREEK 25.0
END DESCRIPTION:
XS GIS Cut Line= 3
      2878750.61     10183875.41      2878668.72     10183161.31
      2878505.68     10182503.08
#Sta/Elev= 30
  4433.3  947.87  4647.7  942.74  4779.1   941.6  4828.2  942.43  4956.6  942.03
  4969.1  940.82  4979.2  934.88  4985.7  929.25  4986.2  928.75  4992.8  929.25
  5009.4  930.07  5019.4  933.37  5029.5  934.86    5130     936  5227.3  939.51
  5263.5  942.16  5268.7  940.98  5301.4   941.3  5366.6  942.84  5430.5  946.02
  5500.5  947.06  5510.8   948.4  5517.1  950.58  5532.8  949.11  5541.7  947.07
  5572.6  951.31  5646.4  955.42  5716.8  961.74  5778.7  969.37  5830.2   972.7
#Mann= 8 ,-1 , 0
  4433.3     .12       0  4647.7     .05       0  4779.1     .12       0
  4985.7     .07       0  4992.8     .12       0  5301.4     .05       0
  5430.5     .12       0  5532.8     .05       0
Bank Sta=4985.7,4992.8
XS Rating Curve= 0 ,0
Exp/Cntr=0.3,0.1

Type RM Length L Ch R = 1 ,11464   ,350,350,350
BEGIN DESCRIPTION:
UPSHAW CREEK 24.0
END DESCRIPTION:
XS GIS Cut Line= 3
      2878933.62     10183792.44      2879051.97     10183187.51
      2879264.88     10182843.57
#Sta/Elev= 30
  4239.4  947.36  4280.4  946.52  4299.6  944.83  4442.7   939.9  4473.1  940.95
  4481.4   939.5    4524  938.73  4564.8  940.18  4615.7  939.63  4625.9  941.67
  4635.9   940.1    4641  941.18  4646.3  939.13  4768.8  936.68  4810.4  935.77
  4890.9  933.51  4942.9  933.58  4955.1  932.94    4970  929.56  4985.4  929.37
  4997.2  926.77  4997.7  926.27  5004.4  926.77  5013.9  928.54  5043.3  941.83
  5085.8  951.87  5159.1  959.05  5174.5  958.71  5238.3  964.01  5260.3  962.94
#Mann= 7 ,-1 , 0
  4239.4     .12       0  4299.6     .05       0  4442.7     .12       0
  4768.8     .05       0  4810.4     .12       0  4997.2     .07       0
  5004.4     .12       0
Bank Sta=4997.2,5004.4
XS Rating Curve= 0 ,0
Exp/Cntr=0.3,0.1

Type RM Length L Ch R = 1 ,11114   ,534,534,534
BEGIN DESCRIPTION:
UPSHAW CREEK 23.0
END DESCRIPTION:
XS GIS Cut Line= 3
      2879045.43     10183872.09      2879340.22      10183390.6
      2879425.35     10182987.87
#Sta/Elev= 30
  4325.8  946.46  4418.4  943.28  4470.5  939.99  4522.7  938.28  4586.6  937.51
  4607.9  936.19  4623.4  936.91  4776.2  935.74    4871  934.14  4890.4   933.1
  4892.8   932.3  4898.5  932.82  4918.5  932.93  4969.6   930.9  4979.8  929.22
  4987.1  922.72  4988.6  922.54  4989.1  922.04  4995.8  922.54  5000.2  922.82
  5010.5  928.22  5041.9   930.3  5061.6  933.95  5086.6   941.5  5092.2  945.48
  5122.9  955.84  5153.5   963.2  5180.9  968.14  5225.1  970.98    5302  966.34
#Mann= 4 ,-1 , 0
  4325.8     .05       0  4898.5     .12       0  4988.6     .07       0
  4995.8     .12       0
Bank Sta=4988.6,4995.8
XS Rating Curve= 0 ,0
Exp/Cntr=0.3,0.1

Type RM Length L Ch R = 1 ,10580   ,357,357,357
BEGIN DESCRIPTION:
UPSHAW CREEK 22.0
END DESCRIPTION:
XS GIS Cut Line= 3
      2879780.04     10184338.09      2879897.08     10183249.75
      2879655.66     10182953.08
#Sta/Elev= 30
  4064.9  942.06  4150.4  938.22  4207.1  937.26  4220.8  937.92  4269.3  936.71
  4452.1  936.01  4472.2  935.06  4512.4  935.16  4532.6  937.03  4538.1  935.32
  4543.1  935.25  4630.1  935.09  4643.2  935.86  4773.9  934.02  4854.4  929.37
  4934.9  927.15    4965  927.68  4975.1  925.33  4985.1  920.39  4998.5  919.08
    4999  918.58    5008  919.08  5015.3  926.62  5025.4  929.05  5289.5  933.06
  5420.4  936.23  5464.4  938.59  5499.6  941.94  5520.4  946.01    5542  947.23
#Mann= 7 ,-1 , 0
  4064.9     .12       0  4207.1     .05       0  4269.3     .12       0
  4998.5     .07       0    5008     .12       0  5289.5     .05       0
  5420.4     .12       0
Bank Sta=4998.5,5008
XS Rating Curve= 0 ,0
Exp/Cntr=0.3,0.1

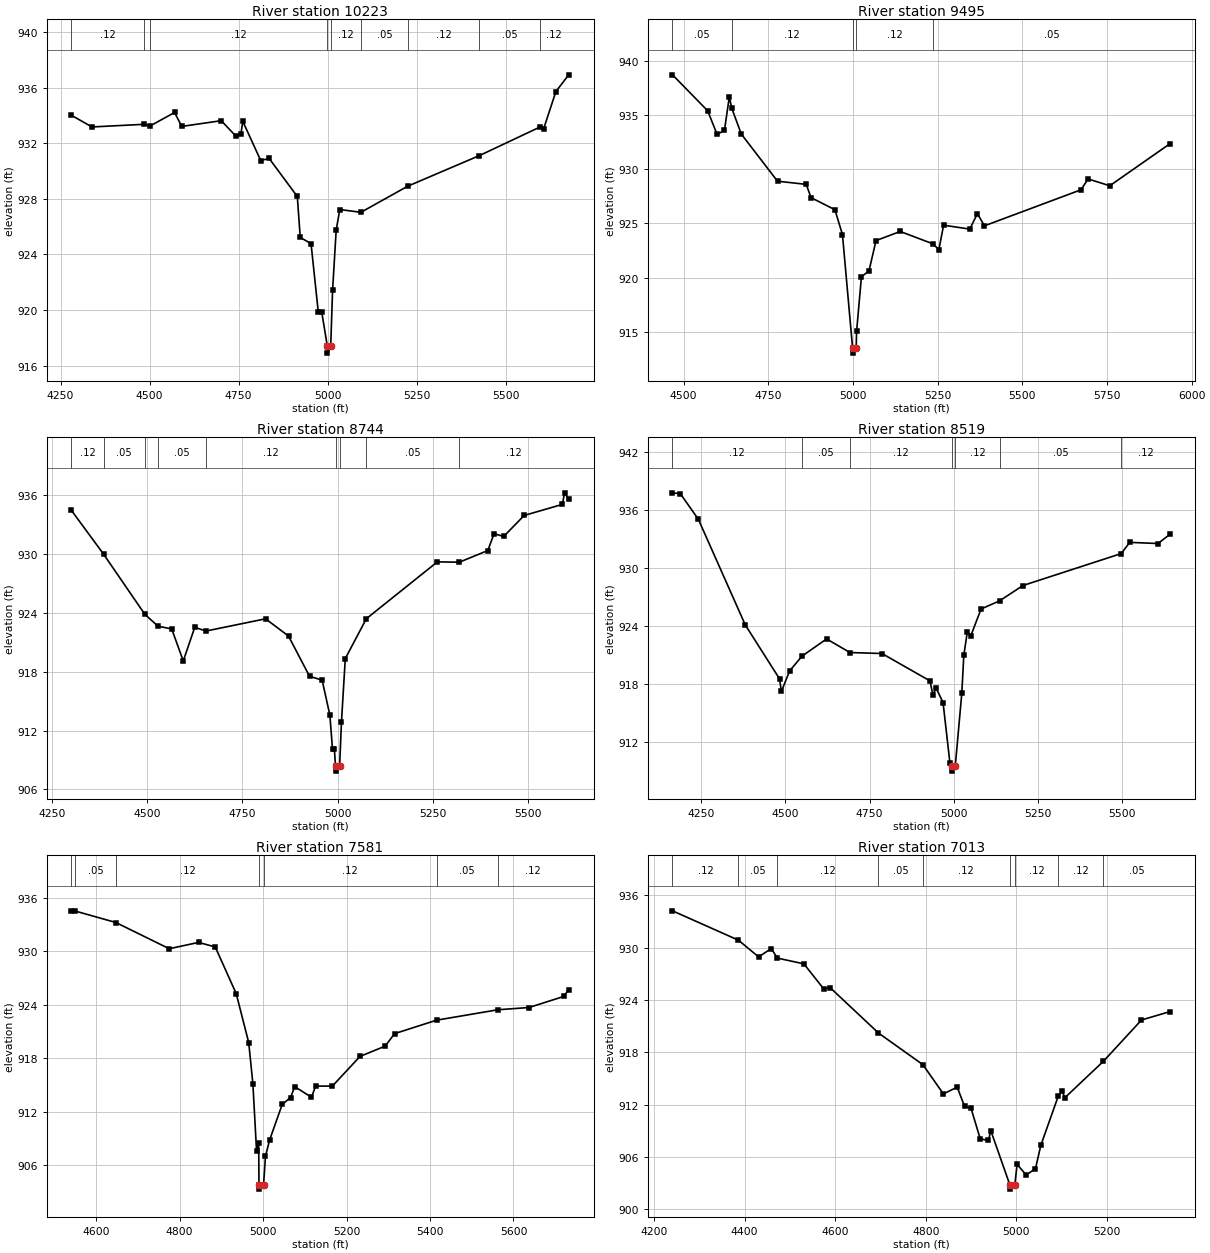
Type RM Length L Ch R = 1 ,10223   ,728,728,728
BEGIN DESCRIPTION:
UPSHAW CREEK 21.0
END DESCRIPTION:
XS GIS Cut Line= 3
      2880139.47     10184160.41      2880249.17     10183315.31
      2880001.92     10182830.51
#Sta/Elev= 30
  4280.6  934.01  4338.4  933.17  4484.3  933.36  4502.1  933.25  4570.3  934.21
  4590.5  933.21  4701.4  933.62  4741.7  932.53  4756.5  932.66  4761.9  933.57
  4812.3  930.75  4835.7  930.91  4914.9  928.17  4923.2  925.22  4953.5  924.78
  4973.7  919.88  4983.7  919.83  4999.2   917.4  4999.7   916.9  5008.7   917.4
    5014  921.43  5024.1  925.75  5034.2  927.23  5093.5  927.03  5225.1  928.91
  5426.2  931.11  5595.9  933.16  5606.7  933.04  5640.9  935.71    5677  936.92
#Mann= 9 ,-1 , 0
  4280.6     .12       0  4484.3     .05       0  4502.1     .12       0
  4999.2     .07       0  5008.7     .12       0  5093.5     .05       0
  5225.1     .12       0  5426.2     .05       0  5595.9     .12       0
Bank Sta=4999.2,5008.7
XS Rating Curve= 0 ,0
Exp/Cntr=0.3,0.1

Type RM Length L Ch R = 1 ,9495    ,751,751,751
BEGIN DESCRIPTION:
UPSHAW CREEK 20.0
END DESCRIPTION:
XS GIS Cut Line= 3
        2881358.     10183826.25      2880804.42      10183377.5
      2880212.98     10182906.96
#Sta/Elev= 30
    4467  938.71  4570.9  935.39  4598.7  933.21  4620.4  933.58  4634.8  936.67
  4641.8  935.65    4670  933.25  4777.1  928.89  4861.8   928.6  4876.2  927.37
  4946.6  926.26  4968.9  923.96  4998.7  913.52  4999.2  913.02  5009.4  913.52
  5010.6  915.02  5024.9  920.07  5047.2  920.61    5068  923.41  5139.4  924.25
  5235.9  923.11  5253.6  922.58  5267.5  924.83  5344.9  924.47  5367.3   925.9
  5388.1  924.77  5673.3   928.1  5694.1   929.1  5758.2  928.47  5935.4  932.34
#Mann= 5 ,-1 , 0
    4467     .05       0  4641.8     .12       0  4998.7     .07       0
  5009.4     .12       0  5235.9     .05       0
Bank Sta=4998.7,5009.4
XS Rating Curve= 0 ,0
Exp/Cntr=0.3,0.1

Type RM Length L Ch R = 1 ,8744    ,225,225,225
BEGIN DESCRIPTION:
UPSHAW CREEK 19.0
END DESCRIPTION:
XS GIS Cut Line= 3
      2881455.67     10183003.11      2880591.51     10182856.67
       2880185.3     10182712.54
#Sta/Elev= 30
  4300.2  934.48  4384.6  930.02  4493.2  923.87  4528.1  922.65  4563.9  922.38
  4594.3  919.11  4624.5  922.54    4654  922.16  4810.7  923.41    4871  921.65
  4926.3  917.54  4959.4  917.15  4979.7  913.59  4986.7  910.09  4991.7  910.08
  4994.6  908.36  4995.1  907.86  5005.4  908.36  5010.2  912.86  5020.3  919.35
  5075.7  923.42  5262.3  929.22  5320.3  929.19  5395.1  930.38  5411.3  932.09
  5436.9  931.82  5490.6  933.96  5591.2  935.09  5596.7  936.27  5607.7   935.6
#Mann= 9 ,-1 , 0
  4300.2     .12       0  4384.6     .05       0  4493.2     .12       0
  4528.1     .05       0    4654     .12       0  4994.6     .07       0
  5005.4     .12       0  5075.7     .05       0  5320.3     .12       0
Bank Sta=4994.6,5005.4
XS Rating Curve= 0 ,0
Exp/Cntr=0.3,0.1

Type RM Length L Ch R = 1 ,8519    ,938,938,938
BEGIN DESCRIPTION:
UPSHAW CREEK 18.0
END DESCRIPTION:
XS GIS Cut Line= 3
       2881577.5     10182951.68      2880866.66     10182679.79
      2880169.82     10182519.49
#Sta/Elev= 30
  4164.9  937.76  4188.3  937.67  4241.8  935.01    4381  924.08  4482.7  918.49
  4488.1  917.19  4512.8  919.33  4549.4  920.85  4622.3  922.63  4691.8  921.22
  4786.6  921.12    4929  918.29  4937.9  916.84  4947.5  917.54    4968  916.04
  4988.5  909.75  4993.4  909.44  4993.9  908.94  5004.2  909.44  5023.6  916.99
  5029.6  920.93  5039.8   923.3  5050.1  922.93  5080.9  925.73  5136.1  926.58
  5205.1  928.16  5496.9  931.47  5522.1  932.63  5605.9  932.51    5641  933.45
#Mann= 7 ,-1 , 0
  4164.9     .12       0  4549.4     .05       0  4691.8     .12       0
  4993.4     .07       0  5004.2     .12       0  5136.1     .05       0
  5496.9     .12       0
Bank Sta=4993.4,5004.2
XS Rating Curve= 0 ,0
Exp/Cntr=0.3,0.1

Type RM Length L Ch R = 1 ,7581    ,568,568,568
BEGIN DESCRIPTION:
UPSHAW CREEK 17.0
END DESCRIPTION:
XS GIS Cut Line= 3
      2882019.68     10182417.74      2881328.52     10182371.88
      2880880.23     10182152.65
#Sta/Elev= 30
  4540.7  934.52  4548.7  934.51  4647.3  933.21  4775.2  930.27  4845.4  930.98
  4885.4  930.47  4935.6  925.24  4965.6  919.75  4975.6  915.13  4984.4  907.58
  4989.5  908.44  4990.2  903.82  4990.7  903.32  5001.2  903.82  5005.7  906.99
  5015.7  908.83  5045.8  912.81  5065.8  913.59  5075.9  914.81    5116  913.62
    5126  914.87  5166.1  914.87  5232.3   918.2  5292.6  919.35  5315.1  920.75
  5415.6  922.26  5562.8  923.43  5637.3  923.68  5720.4  924.92  5732.4  925.69
#Mann= 7 ,-1 , 0
  4540.7     .12       0  4548.7     .05       0  4647.3     .12       0
  4990.2     .07       0  5001.2     .12       0  5415.6     .05       0
  5562.8     .12       0
Bank Sta=4990.2,5001.2
XS Rating Curve= 0 ,0
Exp/Cntr=0.3,0.1

Type RM Length L Ch R = 1 ,7013    ,211,211,211
BEGIN DESCRIPTION:
UPSHAW CREEK 16.0
END DESCRIPTION:
XS GIS Cut Line= 3
      2882075.37     10182041.05      2881741.25     10181942.78
      2881004.25      10181805.2
#Sta/Elev= 30
  4240.9  934.22  4386.6  930.85    4431  928.94  4459.1  929.89  4472.4   928.8
    4531  928.14  4574.8  925.27  4589.2   925.4  4695.7  920.21  4793.8  916.58
    4839  913.23  4869.5     914  4885.9  911.79    4900  911.59  4920.4  908.07
  4938.6  907.89  4943.7  909.02  4985.7  902.81  4986.2  902.31  4996.8  902.81
  5001.7  905.14  5022.1  903.93  5042.4  904.67  5054.1  907.32  5092.7  912.98
  5101.7  913.57  5106.8  912.77  5192.4  916.97  5276.4   921.7  5338.9  922.66
#Mann= 9 ,-1 , 0
  4240.9     .12       0  4386.6     .05       0  4472.4     .12       0
  4695.7     .05       0  4793.8     .12       0  4985.7     .05       0
  4996.8     .12       0  5092.7     .12       0  5192.4     .05       0
Bank Sta=4985.7,4996.8
XS Rating Curve= 0 ,0
Exp/Cntr=0.3,0.1

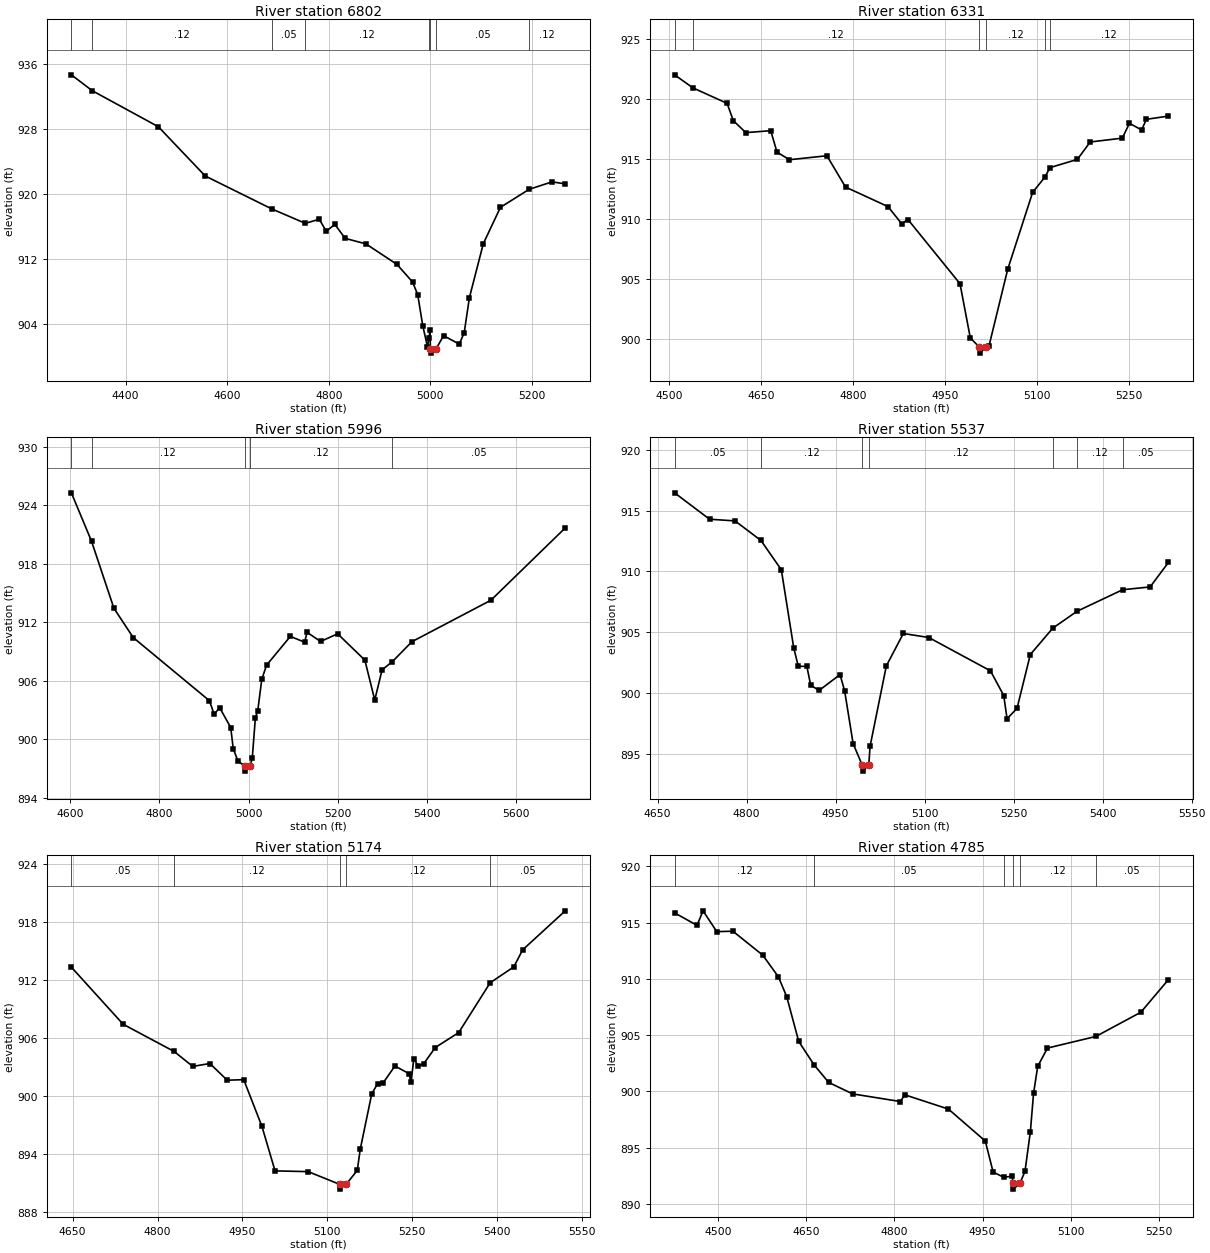
Type RM Length L Ch R = 1 ,6802    ,471,471,471
BEGIN DESCRIPTION:
UPSHAW CREEK 15.0
END DESCRIPTION:
XS GIS Cut Line= 3
      2882013.12     10181811.75      2881434.18     10181689.15
      2881060.27     10181618.56
#Sta/Elev= 30
  4293.2  934.63  4334.2  932.68  4464.4  928.24  4556.8  922.17  4687.7  918.12
  4753.9  916.34  4781.2  916.85    4795  915.37  4811.9  916.21  4832.3  914.49
  4873.2  913.81  4934.3  911.28  4964.9  909.12    4975  907.57  4985.2  903.67
  4994.3  901.14  4997.1  902.25  4999.4  903.16    5000  900.86  5000.5  900.36
  5011.1  900.86  5025.9  902.51  5056.9  901.47  5066.6  902.88  5076.8  907.19
  5104.2  913.84  5137.9  918.31  5194.3  920.53  5239.6  921.45  5265.5   921.2
#Mann= 8 ,-1 , 0
  4293.2     .05       0  4334.2     .12       0  4687.7     .05       0
  4753.9     .12       0  4997.1     .05       0    5000     .05       0
  5011.1     .05       0  5194.3     .12       0
Bank Sta=5000,5011.1
XS Rating Curve= 0 ,0
Exp/Cntr=0.3,0.1

Type RM Length L Ch R = 1 ,6331    ,335,335,335
BEGIN DESCRIPTION:
UPSHAW CREEK 14.0
END DESCRIPTION:
XS GIS Cut Line= 3
       2881819.9     10181320.42      2881238.32     10181215.51
      2881033.76     10181277.81
#Sta/Elev= 30
    4509  922.04    4539  920.95  4594.6  919.66  4604.7  918.22  4625.1  917.22
  4665.7  917.38  4675.9  915.59  4696.2  914.96  4757.2  915.29  4787.6  912.68
  4856.8  911.05  4879.1  909.62  4889.3  909.97  4974.1  904.62  4990.9   900.1
  5005.6  899.33  5006.1  898.83  5016.7  899.33  5021.4  899.44  5051.8  905.81
  5092.5  912.24  5112.6  913.52  5120.7   914.3  5165.4  914.99  5186.3  916.44
  5238.6  916.76  5250.2     918    5270  917.44  5277.9  918.33  5313.8   918.6
#Mann= 6 ,-1 , 0
    4509     .05       0    4539     .12       0  5005.6     .07       0
  5016.7     .12       0  5112.6     .05       0  5120.7     .12       0
Bank Sta=5005.6,5016.7
XS Rating Curve= 0 ,0
Exp/Cntr=0.3,0.1

Type RM Length L Ch R = 1 ,5996    ,459,459,459
BEGIN DESCRIPTION:
UPSHAW CREEK 13.0
END DESCRIPTION:
XS GIS Cut Line= 3
      2881805.72     10181053.12      2881276.11     10180855.27
      2880755.66      10180703.1
#Sta/Elev= 30
  4602.5  925.26  4647.8  920.29  4697.9  913.43  4741.3  910.42  4912.1  903.95
  4922.8  902.55    4935  903.24  4959.9   901.2  4965.5  899.04  4976.2  897.75
    4992  897.23  4992.5  896.73  5003.1  897.23  5008.2  898.06  5015.2   902.2
  5020.5  902.91  5029.5  906.13  5040.2  907.59  5093.6  910.54  5125.6  909.95
  5131.1  910.96  5161.4  910.02  5199.6  910.81  5260.7  908.11  5282.9  904.02
  5299.4  907.12  5322.3  907.95  5366.3     910  5543.4  914.25  5710.1  921.66
#Mann= 5 ,-1 , 0
  4602.5     .05       0  4647.8     .12       0    4992     .07       0
  5003.1     .12       0  5322.3     .05       0
Bank Sta=4992,5003.1
XS Rating Curve= 0 ,0
Exp/Cntr=0.3,0.1

Type RM Length L Ch R = 1 ,5537    ,363,363,363
BEGIN DESCRIPTION:
UPSHAW CREEK 12.0
END DESCRIPTION:
XS GIS Cut Line= 3
      2881918.13     10180734.07      2881574.19     10180445.82
      2881230.49      10180275.6
#Sta/Elev= 30
  4678.6  916.47  4737.5   914.3  4780.5  914.16  4824.2  912.55  4858.5  910.14
  4879.4  903.72  4887.1   902.2  4901.5   902.2    4908  900.64  4922.3  900.22
  4957.4  901.52  4965.2  900.18  4979.5  895.84  4994.8  894.08  4995.3  893.58
  5005.9  894.08    5008  895.61  5035.5  902.24  5064.1   904.9    5107  904.57
  5210.9  901.83  5233.3   899.8  5238.9  897.89  5255.7  898.74  5278.1  903.17
    5316  905.34  5356.9  906.73  5433.7   908.5    5480  908.73  5510.9  910.75
#Mann= 7 ,-1 , 0
  4678.6     .05       0  4824.2     .12       0  4994.8     .07       0
  5005.9     .12       0    5316     .05       0  5356.9     .12       0
  5433.7     .05       0
Bank Sta=4994.8,5005.9
XS Rating Curve= 0 ,0
Exp/Cntr=0.3,0.1

Type RM Length L Ch R = 1 ,5174    ,389,389,389
BEGIN DESCRIPTION:
UPSHAW CREEK 11.0
END DESCRIPTION:
XS GIS Cut Line= 3
      2882003.31     10180622.75      2881882.05     10180038.57
      2881820.31      10179769.7
#Sta/Elev= 30
  4647.8  913.36  4739.3  907.45  4829.2  904.64  4862.3  903.09  4892.5  903.39
  4923.2  901.66  4952.3  901.72  4984.5  896.88  5007.6  892.28  5066.2   892.2
  5121.6  890.89  5122.1  890.39  5133.3  890.89  5152.9  892.33  5158.1   894.5
  5178.5  900.26  5188.7  901.29  5197.9  901.33  5219.4  903.13  5244.4  902.34
  5247.7  901.43  5252.9   903.9  5260.3  903.12  5270.6  903.39  5290.6  905.04
  5332.1  906.59  5387.6  911.74  5429.4  913.39    5445  915.15  5520.3  919.19
#Mann= 5 ,-1 , 0
  4647.8     .05       0  4829.2     .12       0  5121.6     .07       0
  5133.3     .12       0  5387.6     .05       0
Bank Sta=5121.6,5133.3
XS Rating Curve= 0 ,0
Exp/Cntr=0.3,0.1

Type RM Length L Ch R = 1 ,4785    ,184,184,184
BEGIN DESCRIPTION:
UPSHAW CREEK 10.0
END DESCRIPTION:
XS GIS Cut Line= 3
      2882127.77     10180740.64      2882212.94     10180288.59
      2882360.33     10179938.13
#Sta/Elev= 30
  4426.1  915.86  4464.3  914.75  4474.5  916.04  4497.9  914.19  4525.3  914.23
  4576.2   912.1  4602.8  910.17  4616.9  908.41  4637.3  904.44  4663.7  902.34
  4688.2   900.8  4728.9  899.78  4810.3   899.1  4817.6   899.7    4892  898.43
  4954.7  895.59    4968  892.84    4986  892.37  5000.5  892.47  5001.8  891.82
  5002.3  891.32  5013.5  891.82  5022.2   892.9  5031.4  896.43  5036.8  899.83
  5043.9  902.23  5060.5  903.85  5142.7  904.88  5219.3  907.03  5266.3  909.93
#Mann= 6 ,-1 , 0
  4426.1     .12       0  4663.7     .05       0    4986     .12       0
  5001.8     .07       0  5013.5     .12       0  5142.7     .05       0
Bank Sta=5001.8,5013.5
XS Rating Curve= 0 ,0
Exp/Cntr=0.3,0.1