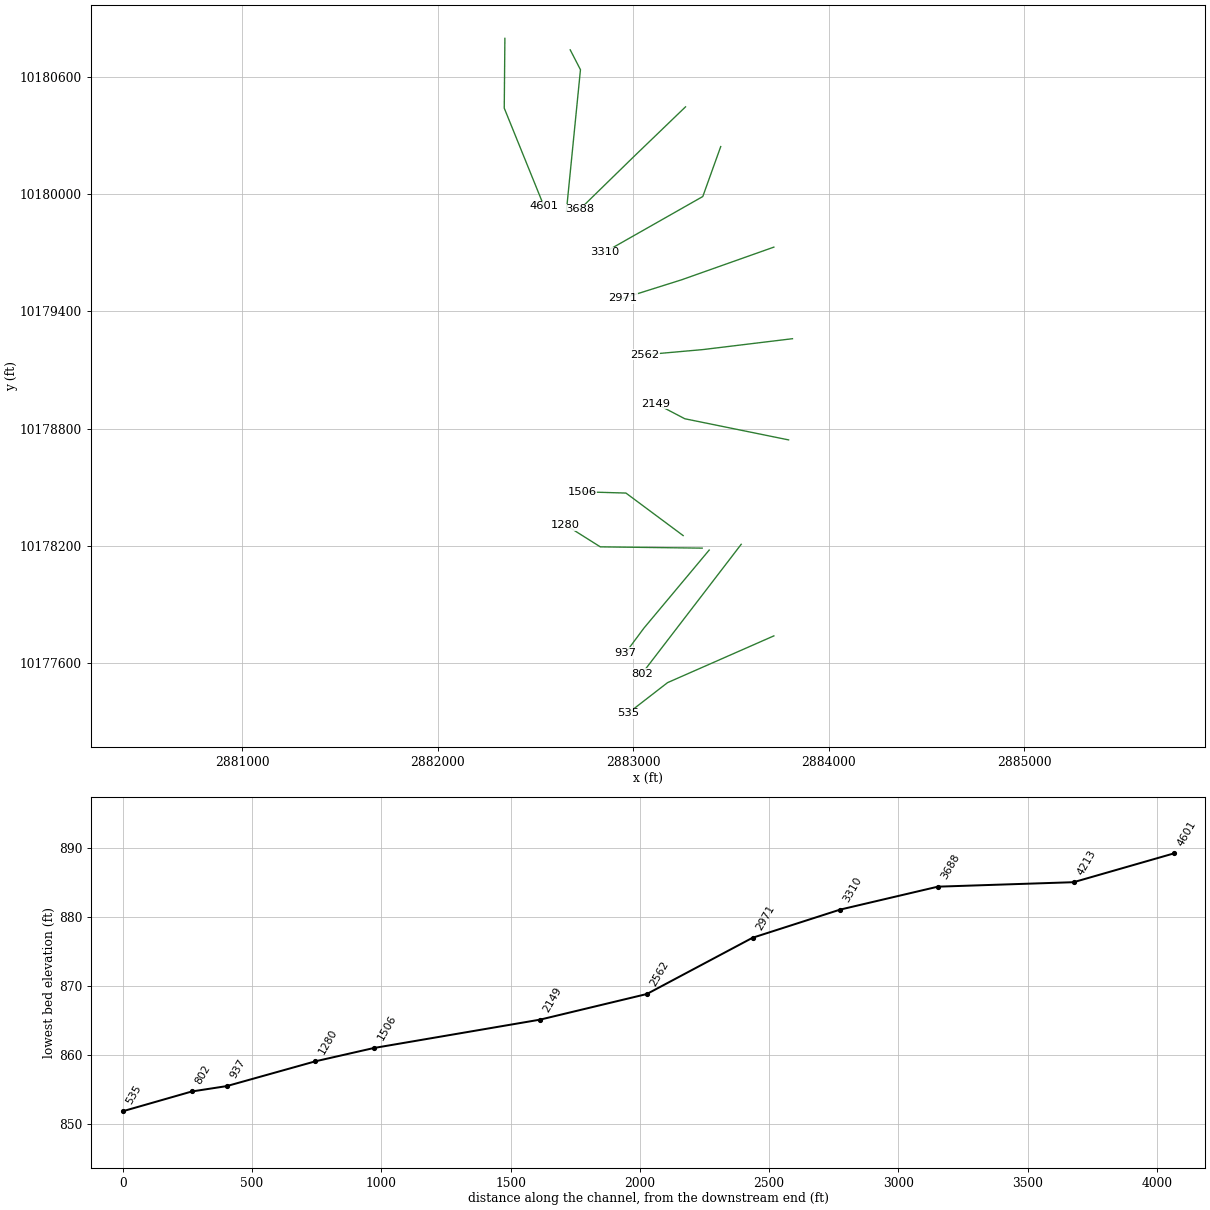
HEC-RAS study UPSHAW CREEK.prj: UPSHAW CREEK Base Level Engineering

--- UPSHAW CREEK.g01 (geometry) --- (continued)

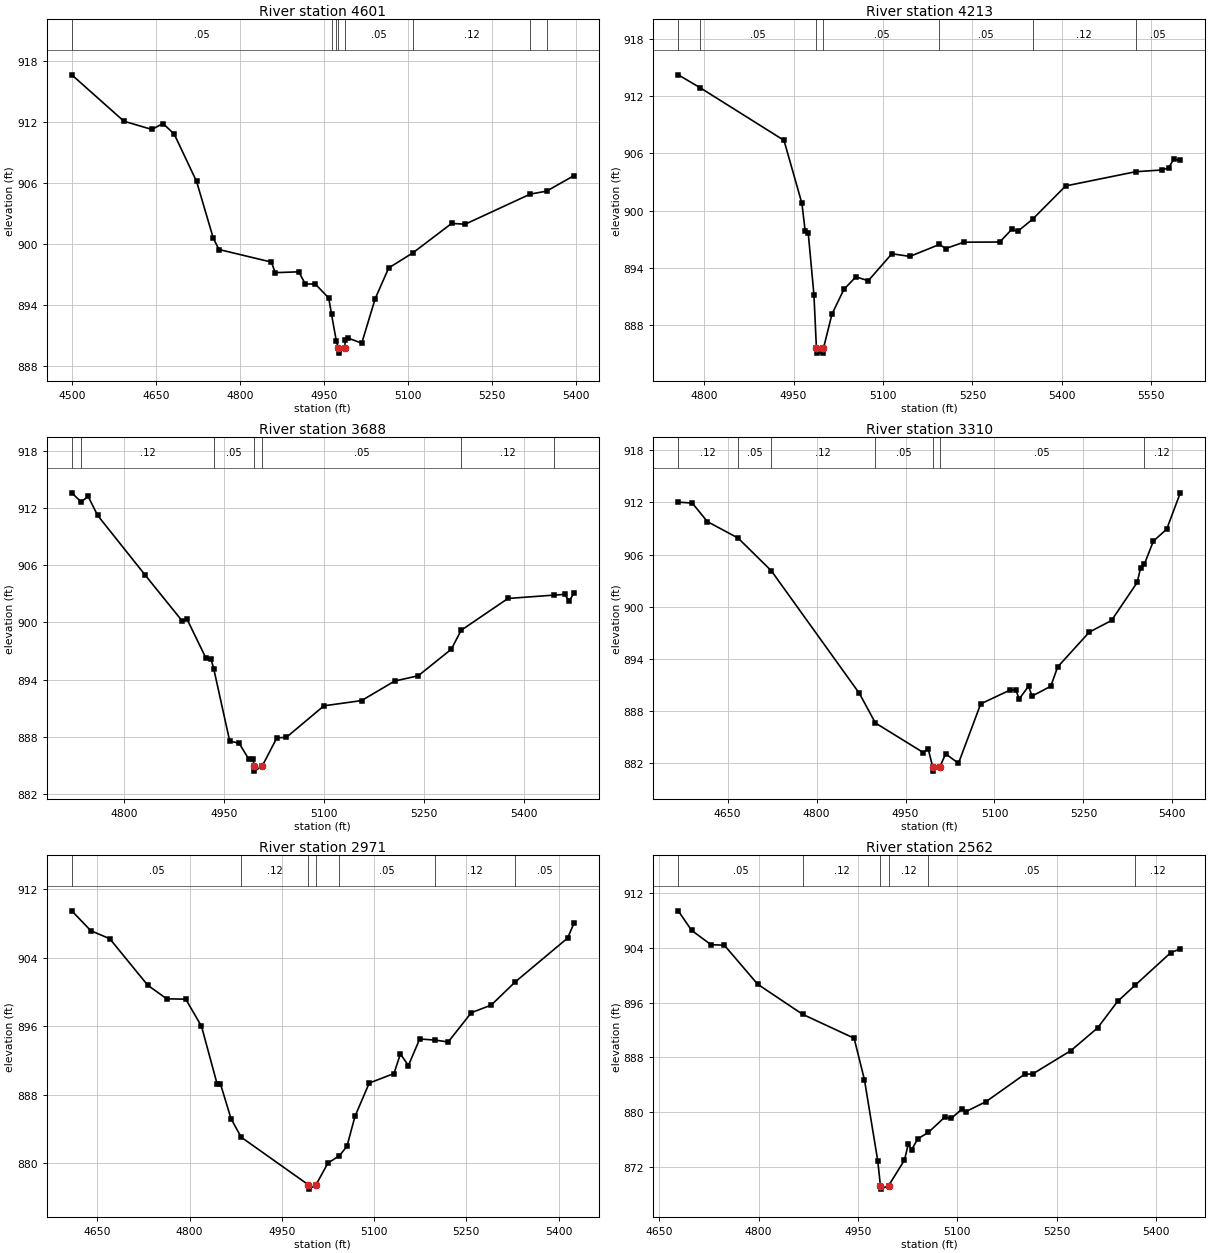
Type RM Length L Ch R = 1 ,4601    ,388,388,388
BEGIN DESCRIPTION:
Mapping XS ae8b79e9
END DESCRIPTION:
XS GIS Cut Line= 3
      2882343.96     10180796.28      2882340.69     10180439.27
      2882543.78     10179938.08
#Sta/Elev= 30
  4499.1  916.66  4592.3  912.09  4642.3  911.28  4662.3  911.86  4682.3  910.82
  4722.3  906.15  4752.3  900.54  4762.3  899.45  4856.1  898.21  4862.8  897.17
    4905  897.25  4916.7  896.05  4934.5  896.05  4958.6  894.67  4963.6  893.06
  4972.2  890.42  4975.6  889.74  4976.1  889.24  4987.3  889.74  4988.1  890.49
  4993.5  890.72  5017.6  890.22  5041.7  894.61  5065.8  897.63  5109.6  899.14
  5178.4  902.02  5202.5  901.94    5319  904.91  5348.2   905.2  5396.9  906.72
#Mann= 8 ,-1 , 0
  4499.1     .05       0  4963.6     .12       0  4972.2     .05       0
  4975.6     .05       0  4987.3     .05       0  5109.6     .12       0
    5319     .05       0  5348.2     .12       0
Bank Sta=4975.6,4987.3
XS Rating Curve= 0 ,0
Exp/Cntr=0.3,0.1

Type RM Length L Ch R = 1 ,4213    ,525,525,525
BEGIN DESCRIPTION:
UPSHAW CREEK 9.0
END DESCRIPTION:
XS GIS Cut Line= 3
      2882678.07     10180737.36      2882730.49      10180635.8
      2882658.42     10179911.87
#Sta/Elev= 30
  4756.7  914.24  4793.1   912.9    4934  907.37  4964.1  900.75  4969.5  897.86
  4974.6  897.69  4984.2   891.2  4988.4  885.56  4988.9  885.06  4999.7  885.06
  5000.2  885.56  5014.4  889.14  5034.5  891.75  5054.6  893.06  5075.3  892.65
  5114.9  895.48    5145   895.2  5194.5  896.45  5205.3  896.03  5235.5  896.69
  5295.8  896.71  5315.9  898.04  5325.9  897.83  5350.8   899.1  5406.3  902.59
  5523.5  904.08  5567.1  904.26  5578.9  904.48  5587.2  905.37  5598.5   905.3
#Mann= 7 ,-1 , 0
  4756.7     .12       0  4793.1     .05       0  4988.4     .07       0
  5000.2     .05       0  5194.5     .05       0  5350.8     .12       0
  5523.5     .05       0
Bank Sta=4988.4,5000.2
XS Rating Curve= 0 ,0
Exp/Cntr=0.3,0.1

Type RM Length L Ch R = 1 ,3688    ,378,378,378
BEGIN DESCRIPTION:
UPSHAW CREEK 8.0
END DESCRIPTION:
XS GIS Cut Line= 3
      2883267.67      10180445.8      2883002.36     10180190.32
      2882727.24     10179921.75
#Sta/Elev= 30
  4721.6   913.6  4735.7  912.64  4746.1  913.23  4760.3  911.24    4831  905.03
  4887.6  900.12  4894.6  900.32  4922.9  896.25  4930.1  896.22  4934.5  895.14
  4958.4  887.56  4972.5  887.34  4986.7   885.7  4993.6  885.66  4994.7  884.91
  4995.2  884.41  5006.9  884.91  5029.1   887.9  5043.3  887.95  5099.7  891.26
  5156.2  891.81  5205.8  893.86  5241.1  894.41  5290.7   897.2  5305.4  899.18
  5375.6  902.52  5444.2  902.87  5460.4  902.95  5467.4  902.27  5474.4  903.05
#Mann= 7 ,-1 , 0
  4721.6     .05       0  4735.7     .12       0  4934.5     .05       0
  4994.7     .05       0  5006.9     .05       0  5305.4     .12       0
  5444.2     .05       0
Bank Sta=4994.7,5006.9
XS Rating Curve= 0 ,0
Exp/Cntr=0.3,0.1

Type RM Length L Ch R = 1 ,3310    ,339,339,339
BEGIN DESCRIPTION:
UPSHAW CREEK 7.0
END DESCRIPTION:
XS GIS Cut Line= 3
      2883447.84     10180242.72      2883356.13     10179987.23
      2882855.71     10179703.12
#Sta/Elev= 30
  4566.6  912.04  4590.3  911.93  4615.7   909.8  4667.4  907.91  4723.6  904.14
    4872  890.04  4899.2  886.62  4980.2  883.21  4988.1  883.68  4995.7  881.58
  4996.2  881.08  5007.9  881.58  5017.7  883.07  5039.3  881.98  5076.8  888.82
    5126   890.4  5135.9  890.45  5141.7  889.38  5157.6  890.86  5163.3  889.71
    5195  890.85  5206.6  893.07    5260  897.08  5297.5  898.42  5340.7  902.79
  5346.5  904.46  5352.7  904.87  5368.1  907.56  5390.5  908.92  5413.5  913.11
#Mann= 7 ,-1 , 0
  4566.6     .12       0  4667.4     .05       0  4723.6     .12       0
  4899.2     .05       0  4995.7     .05       0  5007.9     .05       0
  5352.7     .12       0
Bank Sta=4995.7,5007.9
XS Rating Curve= 0 ,0
Exp/Cntr=0.3,0.1

Type RM Length L Ch R = 1 ,2971    ,409,409,409
BEGIN DESCRIPTION:
UPSHAW CREEK 6.0
END DESCRIPTION:
XS GIS Cut Line= 3
      2883719.69     10179728.45      2883248.03      10179561.4
      2882946.71     10179466.42
#Sta/Elev= 30
  4608.5   909.5  4639.4  907.18  4670.3  906.24    4732  900.81  4762.9  899.22
  4793.8  899.18  4819.4  896.02    4845  889.23  4850.3  889.27  4867.4  885.22
  4883.9  883.06  4993.3  877.49  4993.8  876.99  5005.6  877.49    5025  880.04
  5043.4  880.88  5055.9  881.98  5068.9  885.48  5092.1  889.38  5132.3  890.49
  5142.8  892.78  5155.8  891.43  5174.2  894.53  5199.3   894.4  5220.5  894.18
  5258.1   897.6  5290.5  898.49  5329.7  901.21  5414.7  906.32  5424.8  908.02
#Mann= 7 ,-1 , 0
  4608.5     .05       0  4883.9     .12       0  4993.3     .07       0
  5005.6     .12       0  5043.4     .05       0  5199.3     .12       0
  5329.7     .05       0
Bank Sta=4993.3,5005.6
XS Rating Curve= 0 ,0
Exp/Cntr=0.3,0.1

Type RM Length L Ch R = 1 ,2562    ,413,413,413
BEGIN DESCRIPTION:
UPSHAW CREEK 5.0
END DESCRIPTION:
XS GIS Cut Line= 3
      2883814.74     10179260.05      2883356.13     10179204.36
      2883061.37     10179178.16
#Sta/Elev= 30
  4678.8  909.36  4698.9  906.52  4728.2  904.43  4748.4  904.35  4798.7  898.67
  4866.5  894.29  4944.3   890.8  4959.9  884.75    4980  872.93    4984  869.32
  4984.5  868.82  4996.3  869.32  5020.3  873.05    5026  875.36  5031.1  874.56
  5040.5  876.16  5056.3  877.07  5080.8  879.28  5090.9  879.13  5107.8  880.53
  5112.8   880.1  5143.5  881.57  5201.5  885.54  5213.9   885.6  5271.7  889.01
  5311.9  892.31    5342  896.16  5368.9  898.56  5422.3  903.27  5436.7  903.81
#Mann= 6 ,-1 , 0
  4678.8     .05       0  4866.5     .12       0    4984     .07       0
  4996.3     .12       0  5056.3     .05       0  5368.9     .12       0
Bank Sta=4984,4996.3
XS Rating Curve= 0 ,0
Exp/Cntr=0.3,0.1

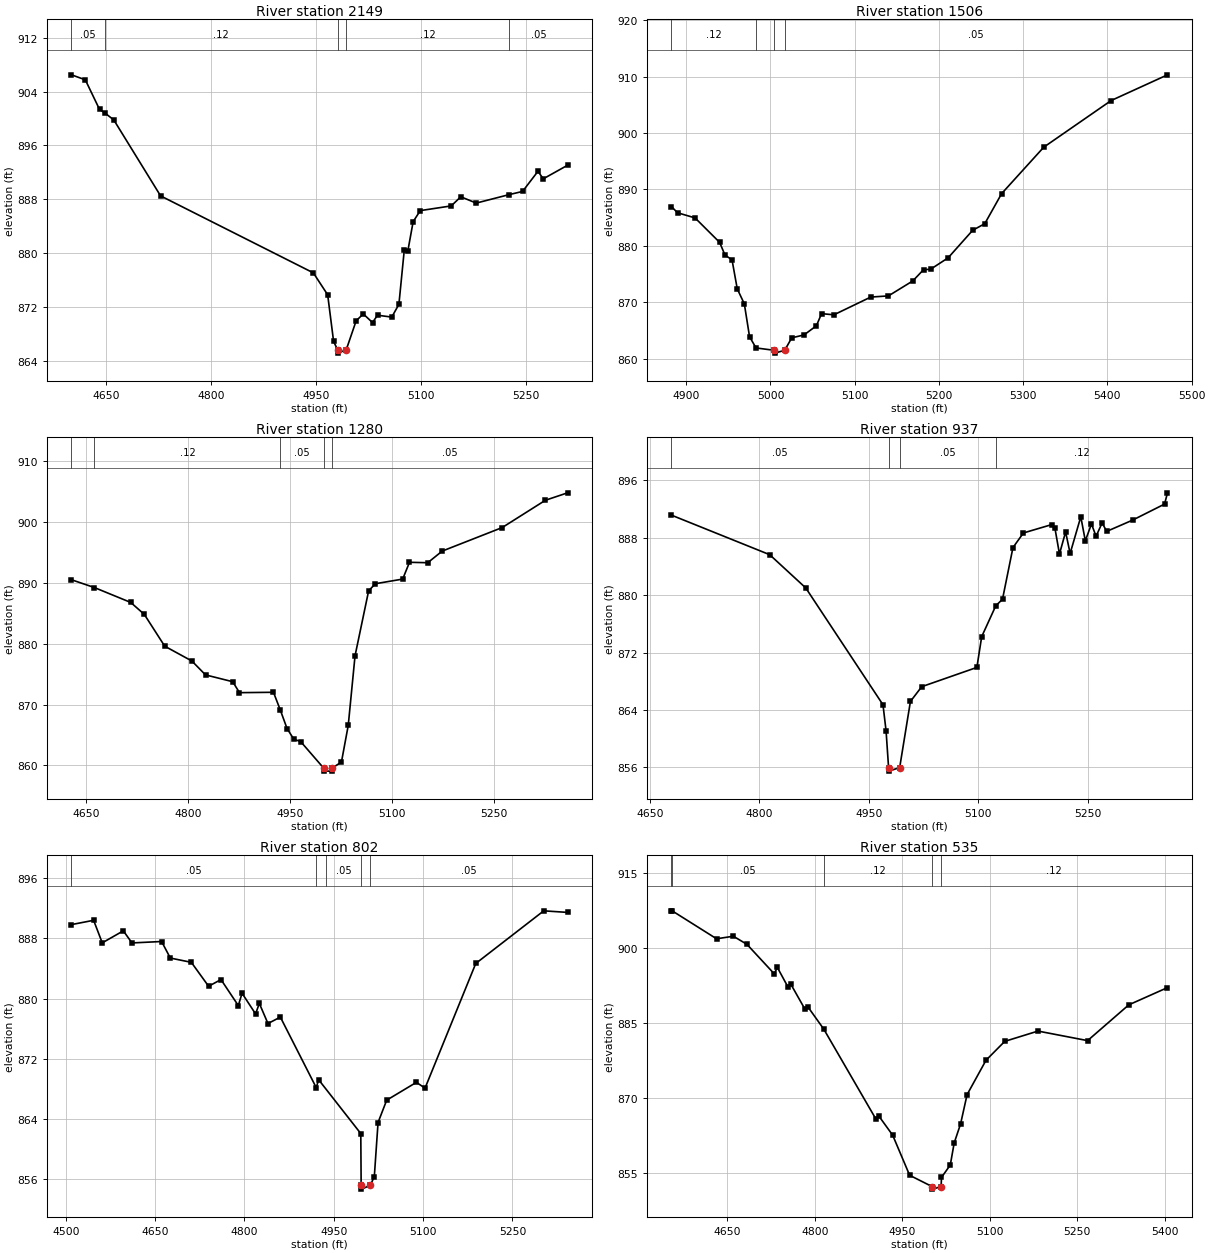
Type RM Length L Ch R = 1 ,2149    ,643,643,643
BEGIN DESCRIPTION:
UPSHAW CREEK 4.0
END DESCRIPTION:
XS GIS Cut Line= 3
      2883795.06      10178742.5      2883264.41     10178850.59
       2883114.8     10178928.65
#Sta/Elev= 30
  4599.9   906.5  4619.7  905.76  4640.1  901.35  4647.3  900.86  4660.5  899.79
  4727.5  888.49  4946.2  877.04  4966.7  873.78  4975.2  866.84  4980.9   865.6
  4981.4   865.1  4993.3   865.6  5007.5  869.91  5017.7  870.93  5030.9  869.65
  5038.1  870.74  5058.5  870.46  5068.7  872.36  5076.4  880.45  5081.5  880.31
  5089.1  884.66  5099.3   886.3  5143.6     887  5157.3  888.36  5179.4  887.42
  5226.9  888.69  5245.7  889.15  5267.8  892.15  5275.4  891.03  5310.2  893.05
#Mann= 5 ,-1 , 0
  4599.9     .05       0  4647.3     .12       0  4980.9     .07       0
  4993.3     .12       0  5226.9     .05       0
Bank Sta=4980.9,4993.3
XS Rating Curve= 0 ,0
Exp/Cntr=0.3,0.1

Type RM Length L Ch R = 1 ,1506    ,226,226,226
BEGIN DESCRIPTION:
UPSHAW CREEK 3.0
END DESCRIPTION:
XS GIS Cut Line= 3
      2883255.66     10178253.13      2882963.05     10178470.62
      2882738.84     10178477.12
#Sta/Elev= 30
  4882.4  886.97  4889.7  885.86  4910.5  884.95  4939.7  880.61    4946  878.37
  4954.4  877.51  4960.6  872.37    4969  869.71  4975.2  863.88  4982.9   861.9
  5004.4  861.48  5004.9  860.98  5016.9  861.48  5025.3  863.69  5039.9  864.21
  5054.5  865.82  5060.7  867.98  5075.3  867.77  5119.1  870.92    5140  871.12
    5169  873.78  5181.7  875.77  5190.1  875.85  5210.9  877.87  5240.1  882.76
  5254.4  883.92  5274.4  889.25  5324.4  897.48  5404.4  905.75  5471.3  910.31
#Mann= 4 ,-1 , 0
  4882.4     .12       0  4982.9     .05       0  5004.4     .07       0
  5016.9     .05       0
Bank Sta=5004.4,5016.9
XS Rating Curve= 0 ,0
Exp/Cntr=0.3,0.1

Type RM Length L Ch R = 1 ,1280    ,343,343,343
BEGIN DESCRIPTION:
Mapping XS bed25fd0
END DESCRIPTION:
XS GIS Cut Line= 3
       2883352.9     10178188.92      2882832.03     10178195.47
      2882655.17     10178306.82
#Sta/Elev= 30
  4628.9  890.51  4662.6  889.23  4716.1  886.78  4736.1  884.81  4766.1  879.59
  4806.1  877.15  4826.1  874.87  4866.1  873.75  4876.1  871.95  4926.1  872.01
  4936.3  869.05  4946.1  866.04  4956.1  864.29  4966.1  863.91  4999.9  859.55
  5000.4  859.05  5011.9  859.05  5012.4  859.55  5026.1  860.54  5036.1  866.57
  5046.1  878.01  5066.1   888.7  5076.1  889.86  5116.2  890.62  5126.2  893.38
  5153.1  893.31  5174.3  895.22  5262.6  899.09  5326.2  903.58  5358.8   904.8
#Mann= 5 ,-1 , 0
  4628.9     .05       0  4662.6     .12       0  4936.3     .05       0
  4999.9     .07       0  5012.4     .05       0
Bank Sta=4999.9,5012.4
XS Rating Curve= 0 ,0
Exp/Cntr=0.5,0.3

Type RM Length L Ch R = 1 ,937     ,135,135,135
BEGIN DESCRIPTION:
UPSHAW CREEK 2.0
END DESCRIPTION:
XS GIS Cut Line= 3
      2883388.89     10178179.09      2883054.77     10177779.47
      2882960.25     10177652.35
#Sta/Elev= 30
  4679.6  891.17  4814.2  885.65  4863.6  881.01 4969.34  864.71 4973.57  861.07
    4977  855.95  4977.5  855.45  4992.2  855.95  5006.9  865.17 5022.36  867.23
  5097.9  869.92  5104.5  874.21  5123.8  878.52    5133  879.43  5147.3  886.64
  5161.6  888.68  5200.5  889.85  5204.8  889.34    5211  885.74  5219.4  888.83
  5225.6  885.82  5240.2  890.94  5246.4  887.58  5254.8  889.94  5261.1  888.22
  5269.4  890.08  5275.7   888.9  5311.1  890.47  5354.9  892.71  5358.9  894.28
#Mann= 4 ,-1 , 0
  4679.6     .05       0    4977     .07       0  4992.2     .05       0
  5123.8     .12       0
Bank Sta=4977,4992.2
XS Rating Curve= 0 ,0
Exp/Cntr=0.5,0.3

Type RM Length L Ch R = 1 ,802     ,267,267,267
BEGIN DESCRIPTION:
Mapping XS 004f2e45
END DESCRIPTION:
XS GIS Cut Line= 2
      2883552.65     10178208.55      2883045.43     10177547.53
#Sta/Elev= 30
  4509.5  889.85  4546.7  890.42  4561.2  887.42  4596.6  889.02  4611.1  887.41
  4660.9   887.6  4675.5   885.4  4710.8  884.83  4739.8  881.65  4760.6  882.54
  4789.7  879.08    4796  880.72  4818.7  877.97    4825  879.37  4839.5  876.69
  4860.3  877.55  4920.5  868.18  4924.7  869.21  4995.4  862.06    4996  855.17
  4996.5  854.67  5011.2  855.17  5018.1  856.32  5024.4  863.53  5038.9   866.5
  5088.8  868.87  5103.3   868.1  5188.5  884.68  5302.7  891.68  5342.7  891.47
#Mann= 5 ,-1 , 0
  4509.5     .05       0  4920.5     .12       0  4936.4     .05       0
    4996     .07       0  5011.2     .05       0
Bank Sta=4996,5011.2
XS Rating Curve= 0 ,0
Exp/Cntr=0.5,0.3

Type RM Length L Ch R = 1 ,535     ,0,0,0
BEGIN DESCRIPTION:
UPSHAW CREEK 1.0
END DESCRIPTION:
XS GIS Cut Line= 3
      2883719.68     10177740.14      2883175.97     10177501.04
      2882972.88     10177343.81
#Sta/Elev= 30
  4554.1  907.44  4555.4  907.44  4631.6  901.85  4660.4  902.36  4683.7  900.74
  4730.4  894.86  4735.9  896.11  4753.8  892.26  4759.2  892.72  4782.6  887.89
    4788  888.28  4815.5  883.78  4904.7  865.84  4910.2  866.36  4933.6  862.59
  4962.7  854.57  5001.4   852.3  5001.9   851.8  5016.7   852.3  5017.3  854.14
  5032.4  856.62  5039.1  861.03  5050.1  864.85  5061.2  870.69  5093.7  877.57
  5125.8  881.34  5182.8   883.4  5267.9  881.49  5338.5  888.64  5404.9  892.09
#Mann= 5 ,-1 , 0
  4554.1     .12       0  4555.4     .05       0  4815.5     .12       0
  5001.4     .07       0  5016.7     .12       0
Bank Sta=5001.4,5016.7
XS Rating Curve= 0 ,0
Exp/Cntr=0.3,0.1

Chan Stop Cuts=-1
Use User Specified Reach Order=0
Composite Channel Slope=5