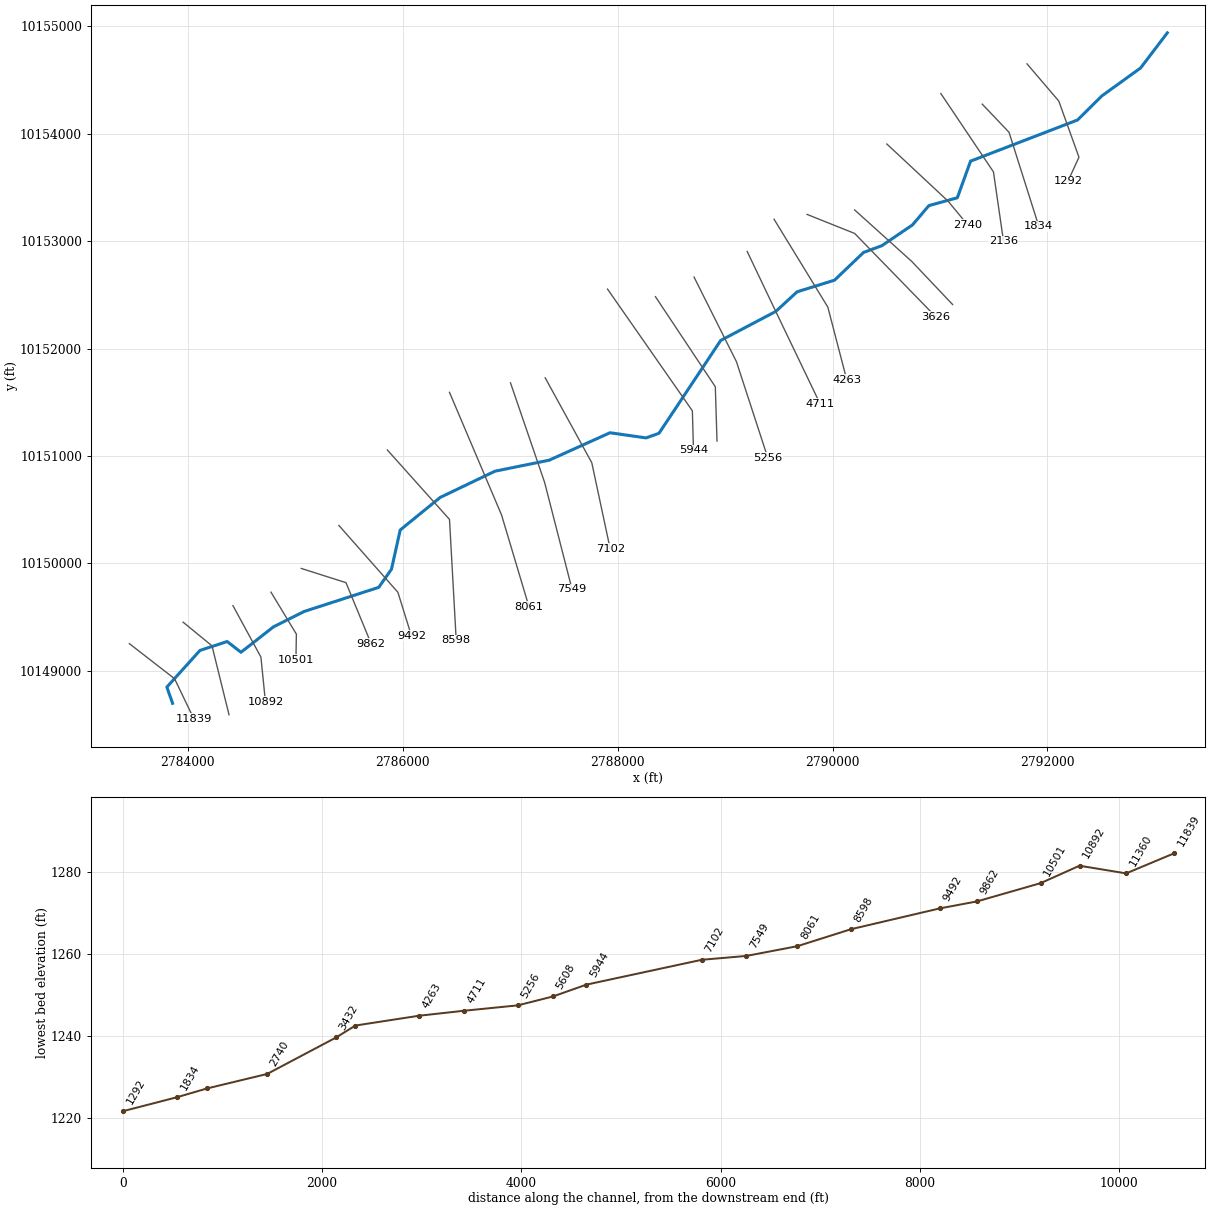
--- KEENER BRANCH.prj (project) ---

Proj Title=KEENER BRANCH Base Level Engineering
Current Plan=p01
Default Exp/Contr=0.3,0.1
English Units
Geom File=g01
Flow File=f01
Plan File=p01
Y Axis Title=Elevation
X Axis Title(PF)=Main Channel Distance
X Axis Title(XS)=Station
BEGIN DESCRIPTION:
KEENER BRANCH
END DESCRIPTION:
DSS Export Rating Curves= 0
DSS Export Rating Curve Sorted= 0
DSS Export Volume Flow Curves= 0
DXF OffsetX= 0
DXF OffsetY= 0
DXF ScaleX= 1
DXF ScaleY= 10

--- KEENER BRANCH.p01 (plan) ---

Plan Title=Multiple Run
Short Identifier=Multiple
Geom File=g01
Flow File=f01
Subcritical Flow
K Sum by GR= 0
Std Step Tol= 0.01
Critical Tol= 0.01
Num of Std Step Trials= 20
Max Error Tol= 0.3
Flow Tol Ratio= 0.001
Split Flow NTrial= 30
Split Flow Tol= 0.02
Split Flow Ratio= 0.02
Log Output Level= 0
Friction Slope Method= 1
Unsteady Friction Slope Method= 2
Unsteady Bridges Friction Slope Method= 1
Parabolic Critical Depth
Global Vel Dist=  1 , 1 , 1
Global Log Level= 0
CheckData=True
Encroach Param= -1, 0, 0, 0
BEGIN DESCRIPTION:
Multiple Run
END DESCRIPTION:

--- KEENER BRANCH.f01 (steady flow) ---

Flow Title=Multiple
Number of Profiles=7
Profile Names=10-year,25-year,50-year,1pct_min,100-year,1pct_plu,500-year
River Rch & RM= KEENER BRANCH,Reach-1,11839
    1150    1990    5015    3781    7442   14651   11012
River Rch & RM= KEENER BRANCH,Reach-1,9862
    1662    2935    7585    5692   11371   22718   16696
River Rch & RM= KEENER BRANCH,Reach-1,4711
    1786    3172    8048    5958   12073   24461   17697
River Rch & RM= KEENER BRANCH,Reach-1,2136
    2018    3608    9223    6819   13882   28257   20294
Boundary for River Rch & Prof#=KEENER BRANCH,Reach-1,1
Up Type=0
Dn Type=3
Dn Slope=0.005
Boundary for River Rch & Prof#=KEENER BRANCH,Reach-1,2
Up Type=0
Dn Type=3
Dn Slope=0.005
Boundary for River Rch & Prof#=KEENER BRANCH,Reach-1,3
Up Type=0
Dn Type=3
Dn Slope=0.005
Boundary for River Rch & Prof#=KEENER BRANCH,Reach-1,4
Up Type=0
Dn Type=3
Dn Slope=0.005
Boundary for River Rch & Prof#=KEENER BRANCH,Reach-1,5
Up Type=0
Dn Type=3
Dn Slope=0.005
Boundary for River Rch & Prof#=KEENER BRANCH,Reach-1,6
Up Type=0
Dn Type=3
Dn Slope=0.005
Boundary for River Rch & Prof#=KEENER BRANCH,Reach-1,7
Up Type=0
Dn Type=3
Dn Slope=0.005

--- KEENER BRANCH.g01 (geometry) ---

Geom Title=Existing Conditions
Program Version=4.10

River Reach=KEENER BRANCH   ,Reach-1
Reach XY= 30
      2783857.75       10148698.       2783804.5       10148849.
       2784112.5       10149190.      2784365.75       10149273.
       2784494.5       10149173.      2784797.25       10149410.
       2785080.5       10149552.      2785776.25       10149777.
        2785895.       10149946.      2785976.25       10150311.
      2786348.25       10150614.       2786857.5       10150858.
      2787363.75       10150961.      2787928.75       10151216.
      2788264.25       10151168.       2788384.5       10151211.
        2788959.       10152075.       2789471.5       10152345.
       2789670.5       10152528.       2790018.5       10152636.
      2790288.25       10152894.        2790459.       10152957.
       2790743.5       10153150.       2790896.5       10153330.
      2791161.25       10153403.      2791284.75       10153744.
      2792280.25       10154127.       2792506.5       10154351.
        2792867.       10154611.      2793115.75       10154938.

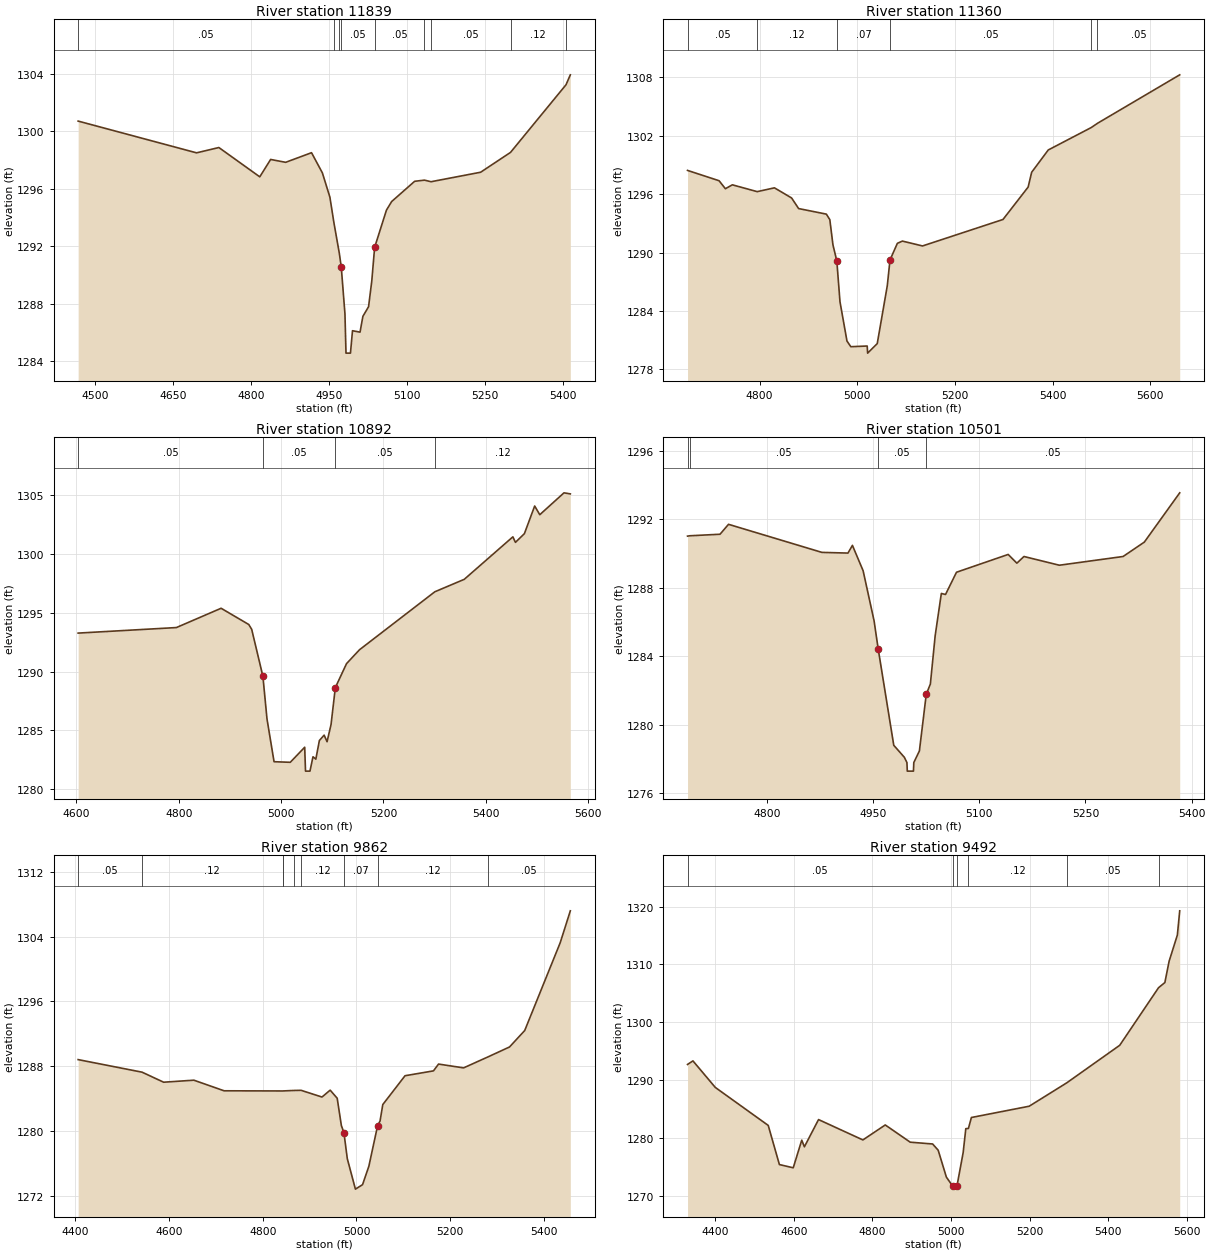
Type RM Length L Ch R = 1 ,11839   ,479,479,479
BEGIN DESCRIPTION:
KEENER BRANCH 23.0
END DESCRIPTION:
XS GIS Cut Line= 3
      2783455.67     10149253.12      2783876.25       10148927.
      2784055.68     10148553.13
#Sta/Elev= 30
  4467.8  1300.7  4695.6 1298.49  4738.5 1298.86  4817.2 1296.82  4838.1 1298.03
    4867 1297.83  4916.8  1298.5  4937.6  1297.1  4952.1 1295.41  4959.8 1293.64
  4970.3 1291.49    4974 1290.54  4981.1 1287.28  4983.1 1284.55  4991.7 1284.55
  4995.6 1286.11  5010.1 1286.01  5015.6 1287.11  5026.5 1287.78  5032.7 1289.57
  5038.2 1291.91  5060.9  1294.5  5070.9  1295.1  5115.2 1296.51  5134.1 1296.59
  5146.7 1296.48  5242.1 1297.14  5299.6 1298.52  5406.4 1303.23  5414.7 1303.92
#Mann= 9 ,-1 , 0
  4467.8     .05       0  4959.8     .12       0  4970.3     .05       0
    4974     .05       0  5038.2     .05       0  5134.1     .12       0
  5146.7     .05       0  5299.6     .12       0  5406.4     .05       0
Bank Sta=4974,5038.2
XS Rating Curve= 0 ,0
Exp/Cntr=0.3,0.1

Type RM Length L Ch R = 1 ,11360   ,468,468,468
BEGIN DESCRIPTION:
KEENER BRANCH 22.0
END DESCRIPTION:
XS GIS Cut Line= 3
      2783955.71     10149453.09       2784224.5       10149233.
      2784382.93     10148591.78
#Sta/Elev= 30
  4652.6 1298.44  4717.2 1297.38  4730.1 1296.56  4744.4 1296.96  4795.2 1296.26
  4830.6 1296.65  4865.7 1295.61  4880.1 1294.52  4936.9 1293.95    4944 1293.38
  4950.4 1290.79  4958.3 1289.14  4964.8 1284.95  4979.1 1280.91    4987 1280.33
  5020.5  1280.4  5021.4 1279.67  5041.1 1280.65  5061.7 1286.61  5067.2 1289.24
  5082.3 1290.95  5092.6 1291.18  5133.8 1290.68  5298.6  1293.4  5350.1 1296.73
  5357.3 1298.25  5391.3 1300.54  5479.2 1302.84  5492.1 1303.28  5660.5 1308.26
#Mann= 6 ,-1 , 0
  4652.6     .05       0  4795.2     .12       0  4958.3     .07       0
  5067.2     .05       0  5479.2     .12       0  5492.1     .05       0
Bank Sta=4958.3,5067.2
XS Rating Curve= 0 ,0
Exp/Cntr=0.3,0.1

Type RM Length L Ch R = 1 ,10892   ,391,391,391
BEGIN DESCRIPTION:
KEENER BRANCH 21.0
END DESCRIPTION:
XS GIS Cut Line= 3
      2784419.38     10149607.42       2784679.8     10149128.24
      2784721.72     10148713.73
#Sta/Elev= 30
  4603.3 1293.27  4795.3 1293.74  4882.7 1295.38  4936.8    1294  4942.5 1293.59
  4964.4  1289.6  4972.4 1285.98  4986.2 1282.34  5017.9 1282.29  5046.1 1283.57
  5047.7 1281.54  5056.4 1281.54  5062.3 1282.76  5067.9 1282.56  5074.8 1284.14
  5084.1  1284.6  5089.8 1284.04  5097.6  1285.5    5106 1288.64  5127.8 1290.67
  5153.1 1291.85  5300.4 1296.78    5358 1297.84    5453 1301.45    5458 1300.98
  5475.5 1301.72  5495.6 1304.07  5505.6 1303.33  5552.9 1305.19  5565.3  1305.1
#Mann= 4 ,-1 , 0
  4603.3     .05       0  4964.4     .05       0    5106     .05       0
  5300.4     .12       0
Bank Sta=4964.4,5106
XS Rating Curve= 0 ,0
Exp/Cntr=0.3,0.1

Type RM Length L Ch R = 1 ,10501   ,639,639,639
BEGIN DESCRIPTION:
KEENER BRANCH 20.0
END DESCRIPTION:
XS GIS Cut Line= 3
      2784773.58     10149732.36      2785009.96     10149341.74
      2785005.68     10149103.15
#Sta/Elev= 30
    4688 1291.01  4690.9 1291.03  4733.9 1291.12  4745.9  1291.7  4877.8 1290.06
  4914.6 1290.02  4920.9 1290.47    4936 1288.99  4951.5 1286.06  4957.3 1284.42
  4979.3 1278.79  4994.2 1278.09  4997.9 1277.78  4998.4 1277.28  5007.1 1277.28
  5007.6 1277.78  5015.5 1278.46  5025.2 1281.77    5031 1282.37  5037.8  1285.2
  5046.5 1287.66  5052.4  1287.6  5067.9  1288.9  5140.9 1289.94  5153.2 1289.43
  5163.2 1289.82  5213.2 1289.31  5303.2 1289.82  5333.2 1290.66  5383.2 1293.54
#Mann= 4 ,-1 , 0
    4688     .12       0  4690.9     .05       0  4957.3     .05       0
  5025.2     .05       0
Bank Sta=4957.3,5025.2
XS Rating Curve= 0 ,0
Exp/Cntr=0.3,0.1

Type RM Length L Ch R = 1 ,9862    ,370,370,370
BEGIN DESCRIPTION:
KEENER BRANCH 19.0
END DESCRIPTION:
XS GIS Cut Line= 3
      2785055.73      10149953.1      2785471.47     10149820.94
      2785705.69     10149253.09
#Sta/Elev= 30
    4406 1288.81  4542.4 1287.26  4588.5 1286.02    4653 1286.27  4717.5 1284.96
  4842.2 1284.94  4842.3 1284.94  4865.8    1285  4881.8 1285.02  4926.4 1284.19
  4943.9 1285.04  4958.9 1284.04  4967.8 1280.67  4973.2 1279.81  4980.5 1276.57
  4997.8 1272.82    5013 1273.37  5026.5 1275.65    5045 1280.61  5050.4 1281.24
  5056.2 1283.26  5103.7 1286.82  5164.4 1287.42  5175.2 1288.26  5228.7 1287.79
  5280.9 1289.15  5326.7 1290.37  5359.1  1292.4  5434.8 1303.23  5456.5 1307.18
#Mann= 9 ,-1 , 0
    4406     .05       0  4542.4     .12       0  4842.2     .05       0
  4842.3     .12       0  4865.8     .05       0  4881.8     .12       0
  4973.2     .07       0    5045     .12       0  5280.9     .05       0
Bank Sta=4973.2,5045
XS Rating Curve= 0 ,0
Exp/Cntr=0.3,0.1

Type RM Length L Ch R = 1 ,9492    ,894,894,894
BEGIN DESCRIPTION:
KEENER BRANCH 18.0
END DESCRIPTION:
XS GIS Cut Line= 3
      2785405.67     10150353.13       2785954.8     10149731.12
      2786080.47     10149327.35
#Sta/Elev= 30
  4329.4  1292.7  4343.2 1293.31  4400.1 1288.72  4534.8 1282.15  4563.2 1275.38
  4598.4 1274.82  4620.1  1279.6  4626.8 1278.45  4662.8 1283.16  4775.7 1279.64
  4832.6 1282.23  4896.2 1279.25  4953.1 1278.94  4967.3 1277.86  4988.2  1273.2
  5004.5 1271.63    5005 1271.13    5015 1271.63  5030.9 1277.47  5037.6 1281.59
  5044.3 1281.63  5051.8 1283.52  5198.9 1285.47  5294.4 1289.51  5429.3 1296.01
  5528.2 1305.98  5544.2 1306.86    5555 1310.55    5576 1315.08    5582 1319.27
#Mann= 6 ,-1 , 0
  4329.4     .05       0  5004.5     .05       0    5015     .05       0
  5044.3     .12       0  5294.4     .05       0  5528.2     .12       0
Bank Sta=5004.5,5015
XS Rating Curve= 0 ,0
Exp/Cntr=0.3,0.1

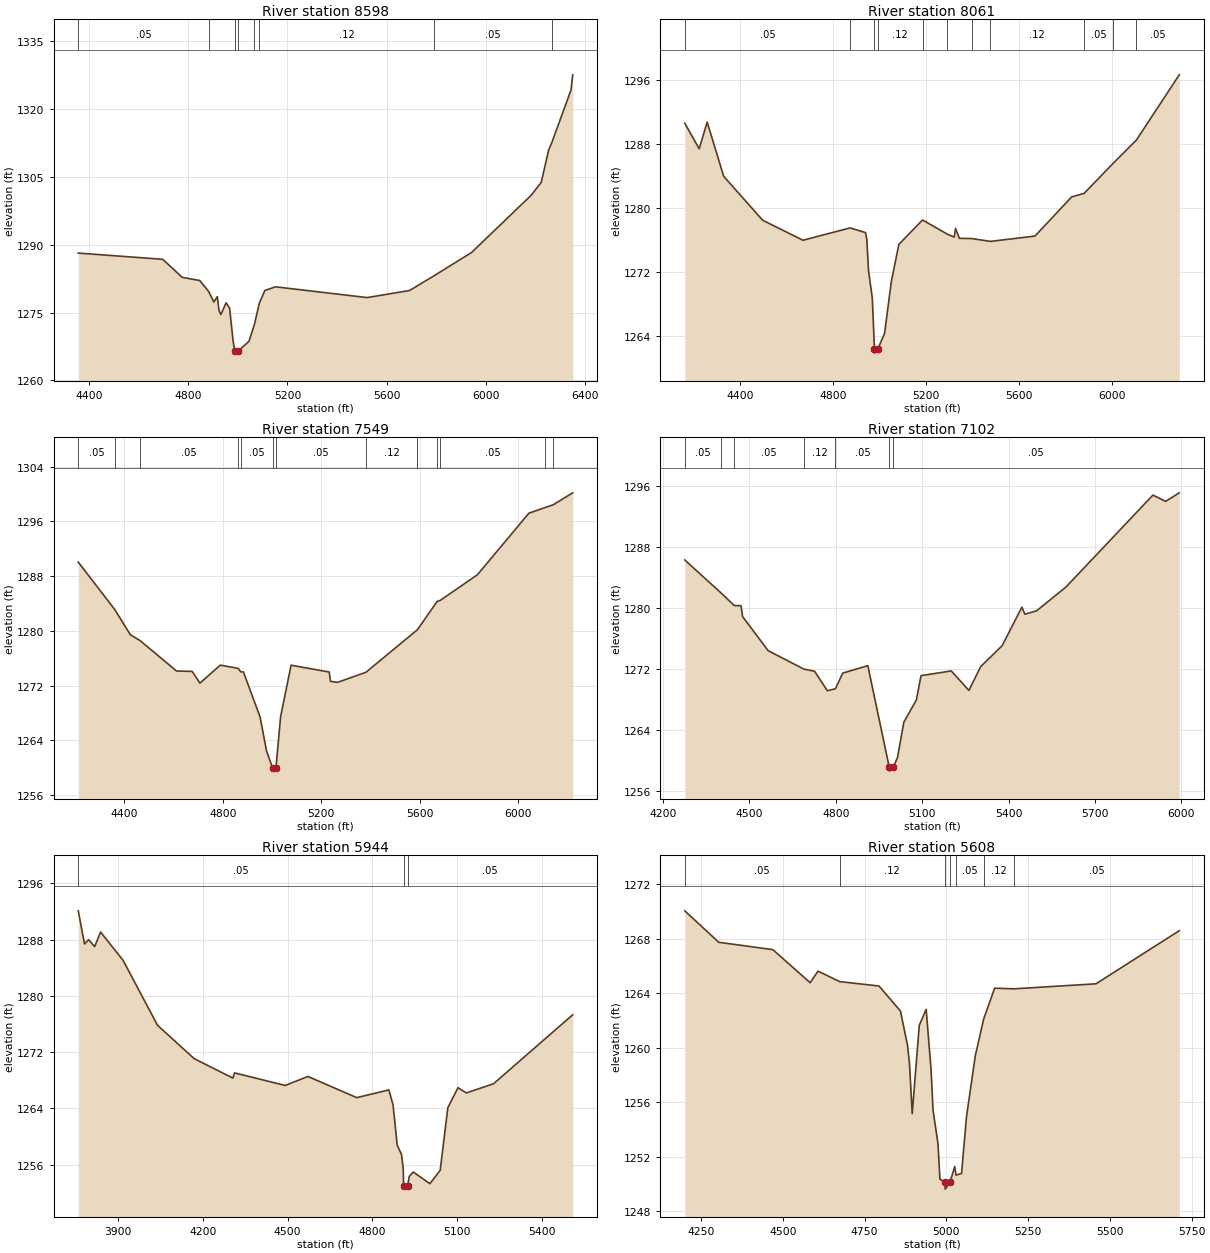
Type RM Length L Ch R = 1 ,8598    ,537,537,537
BEGIN DESCRIPTION:
KEENER BRANCH 17.0
END DESCRIPTION:
XS GIS Cut Line= 3
      2785856.87     10151055.34      2786435.01     10150409.49
      2786497.41     10149286.34
#Sta/Elev= 30
  4357.6 1288.15    4698 1286.77  4776.5 1282.78  4846.8 1282.09  4883.2 1279.64
  4903.6 1277.33  4917.8 1278.51  4924.5 1275.46    4932 1274.56    4953 1277.15
  4967.2 1275.96  4981.4 1268.67  4988.5 1266.53    4989 1266.03  5002.6 1266.53
  5045.1 1268.64  5067.3  1272.4  5087.1 1277.09  5109.2 1279.88  5151.9 1280.69
  5521.3 1278.31  5691.9 1279.87  5791.8 1283.17  5941.9 1288.28  6182.3 1300.95
  6222.3 1303.77  6252.4 1310.94  6265.6 1312.64  6342.5 1324.23  6349.3 1327.56
#Mann= 8 ,-1 , 0
  4357.6     .05       0  4883.2     .12       0  4988.5     .07       0
  5002.6     .12       0  5067.3     .05       0  5087.1     .12       0
  5791.8     .05       0  6265.6     .12       0
Bank Sta=4988.5,5002.6
XS Rating Curve= 0 ,0
Exp/Cntr=0.3,0.1

Type RM Length L Ch R = 1 ,8061    ,512,512,512
BEGIN DESCRIPTION:
KEENER BRANCH 16.0
END DESCRIPTION:
XS GIS Cut Line= 3
        2786435.     10151591.82      2786919.39     10150451.15
      2787174.42     10149597.59
#Sta/Elev= 30
  4161.6 1290.59  4223.6  1287.4  4258.2 1290.73  4329.1 1283.97    4497 1278.48
  4670.8 1275.98  4873.7 1277.52  4940.3 1276.93  4945.8 1276.07  4953.3 1272.16
  4969.4 1268.76  4978.8 1262.39  4979.3 1261.89  4992.9 1262.39  5022.2 1264.35
  5051.2 1270.77  5083.7 1275.46  5185.8 1278.51  5293.3 1276.73  5322.3 1276.38
  5327.8 1277.46  5344.4 1276.22  5398.1 1276.19  5478.4 1275.84  5670.2  1276.5
  5828.2 1281.39  5881.8 1281.83    6006 1285.55  6107.3 1288.49  6291.7 1296.63
#Mann= 11 ,-1 , 0
  4161.6     .05       0  4873.7     .12       0  4978.8     .07       0
  4992.9     .12       0  5185.8     .05       0  5293.3     .12       0
  5398.1     .05       0  5478.4     .12       0  5881.8     .05       0
    6006     .12       0  6107.3     .05       0
Bank Sta=4978.8,4992.9
XS Rating Curve= 0 ,0
Exp/Cntr=0.3,0.1

Type RM Length L Ch R = 1 ,7549    ,447,447,447
BEGIN DESCRIPTION:
KEENER BRANCH 15.0
END DESCRIPTION:
XS GIS Cut Line= 3
      2787002.73     10151680.29      2787320.43     10150753.24
      2787575.64     10149758.43
#Sta/Elev= 30
  4213.3 1290.06  4360.9 1283.15    4425 1279.43  4463.3 1278.61  4612.6 1274.13
  4675.4 1274.09  4707.2 1272.37  4789.7    1275  4862.2 1274.53  4872.9 1274.02
  4883.6 1274.01  4951.4 1267.41  4977.4 1262.46  5001.7 1260.01  5002.2 1259.51
  5015.8 1260.01  5034.7 1267.49  5077.1 1274.99    5232 1273.99  5237.2 1272.63
  5265.7 1272.48  5381.1 1273.96  5590.2 1280.18  5669.9 1284.31  5682.2 1284.45
  5833.2  1288.2  6042.3  1297.2  6109.7 1298.05  6141.5 1298.44  6220.3 1300.18
#Mann= 13 ,-1 , 0
  4213.3     .05       0  4360.9     .12       0  4463.3     .05       0
  4862.2     .12       0  4872.9     .05       0  5001.7     .05       0
  5015.8     .05       0  5381.1     .12       0  5590.2     .05       0
  5669.9     .12       0  5682.2     .05       0  6109.7     .12       0
  6141.5     .05       0
Bank Sta=5001.7,5015.8
XS Rating Curve= 0 ,0
Exp/Cntr=0.3,0.1

Type RM Length L Ch R = 1 ,7102    ,1158,1158,1158
BEGIN DESCRIPTION:
KEENER BRANCH 14.0
END DESCRIPTION:
XS GIS Cut Line= 3
      2787325.62     10151727.23      2787759.19     10150937.15
      2787929.81     10150138.61
#Sta/Elev= 30
  4275.3 1286.28  4402.5 1281.91    4447  1280.3  4470.6 1280.28  4476.3 1278.84
  4565.2 1274.37    4689 1271.96  4726.5 1271.67  4770.5 1269.12  4798.6 1269.38
    4824 1271.43  4911.2 1272.41  4985.7 1259.07  4986.2 1258.57  4999.8 1259.07
  5014.5 1260.38  5036.3 1264.99  5079.9 1267.92    5096  1271.1  5201.1 1271.72
  5262.5 1269.16  5303.4 1272.29  5377.6 1275.02  5446.5 1280.09  5456.8 1279.16
  5497.7 1279.61  5599.9 1282.74  5901.6 1294.79  5945.9 1293.97  5993.1 1295.09
#Mann= 7 ,-1 , 0
  4275.3     .05       0  4402.5     .12       0    4447     .05       0
    4689     .12       0  4798.6     .05       0  4985.7     .05       0
  4999.8     .05       0
Bank Sta=4985.7,4999.8
XS Rating Curve= 0 ,0
Exp/Cntr=0.3,0.1

Type RM Length L Ch R = 1 ,5944    ,336,336,336
BEGIN DESCRIPTION:
KEENER BRANCH 12.0
END DESCRIPTION:
XS GIS Cut Line= 3
      2787905.71     10152553.08      2788695.43      10151419.9
      2788705.68     10151053.16
#Sta/Elev= 30
    3760  1292.1  3782.2 1287.38  3796.5    1288    3818 1287.01  3838.9 1289.08
  3918.4 1285.06  4040.3 1275.81  4169.6 1271.07  4306.6  1268.3  4312.7 1269.04
  4491.6 1267.25  4571.9 1268.53  4744.6 1265.52  4858.1 1266.62  4872.9 1264.48
  4887.7 1258.73  4902.6 1257.45  4908.7  1255.5  4910.2    1253  4910.7  1252.5
  4924.6    1253  4930.1 1254.29  4944.4 1254.94  5003.2 1253.27  5039.6 1255.19
  5066.6 1264.08  5102.4 1266.93  5132.1 1266.19    5228 1267.49  5508.1 1277.31
#Mann= 3 ,-1 , 0
    3760     .05       0  4910.2     .03       0  4924.6     .05       0
Bank Sta=4910.2,4924.6
XS Rating Curve= 0 ,0
Exp/Cntr=0.3,0.1

Type RM Length L Ch R = 1 ,5608    ,352,352,352
BEGIN DESCRIPTION:
KEENER BRANCH 11.0
END DESCRIPTION:
XS GIS Cut Line= 3
      2788351.67     10152482.42      2788908.97     10151643.86
       2788924.6     10151138.67
#Sta/Elev= 30
  4199.9 1270.05  4303.8 1267.74  4469.2  1267.2  4583.4 1264.77  4607.3 1265.62
  4673.8 1264.85  4793.9 1264.53  4859.5 1262.69  4881.1 1260.18  4887.1 1258.85
  4895.5 1255.15  4917.1 1261.64  4938.2 1262.82  4953.2 1258.37  4959.2 1255.41
  4974.3 1252.95  4980.3 1250.34  4995.8 1250.11  4996.3 1249.61  5011.2 1250.11
  5025.4 1251.27  5029.6 1250.64  5046.4 1250.76  5061.5 1254.93  5088.5 1259.41
    5114  1262.1  5147.6 1264.37    5206 1264.32  5457.6 1264.69  5712.2 1268.59
#Mann= 7 ,-1 , 0
  4199.9     .05       0  4673.8     .12       0  4995.8     .07       0
  5011.2     .12       0  5029.6     .05       0    5114     .12       0
    5206     .05       0
Bank Sta=4995.8,5011.2
XS Rating Curve= 0 ,0
Exp/Cntr=0.3,0.1

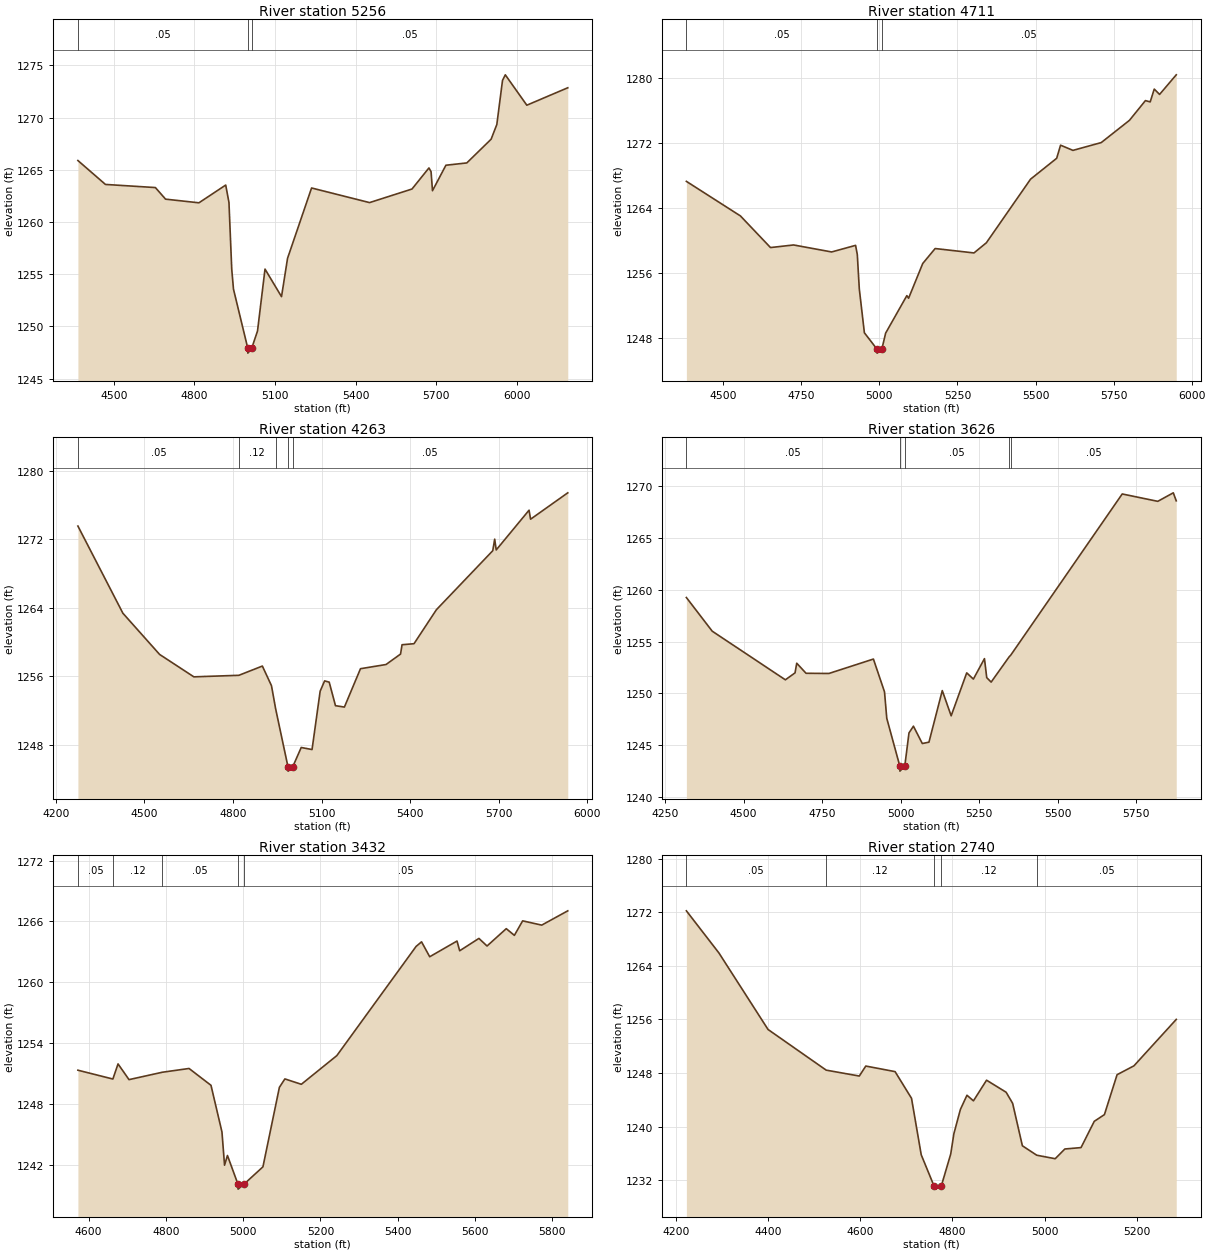
Type RM Length L Ch R = 1 ,5256    ,545,545,545
BEGIN DESCRIPTION:
KEENER BRANCH 10.0
END DESCRIPTION:
XS GIS Cut Line= 3
      2788711.07     10152664.67      2789105.68     10151877.07
      2789397.54     10150982.19
#Sta/Elev= 30
  4366.4 1265.89  4468.8  1263.6  4654.6  1263.3  4692.5 1262.19  4816.6 1261.84
  4916.2 1263.54  4928.3 1261.87  4938.6 1255.49  4945.1 1253.57    4998 1247.94
  4998.5 1247.44  5013.4 1247.94  5034.5 1249.56  5062.4 1255.49  5123.8 1252.85
  5146.2 1256.52  5235.6 1263.26  5451.3 1261.86  5609.1 1263.16  5672.2 1265.18
  5680.1 1264.82  5685.4    1263  5735.3 1265.44    5813 1265.66  5903.4 1267.93
  5924.7 1269.34  5945.9 1273.57  5956.2  1274.1  6036.3 1271.19  6188.6 1272.86
#Mann= 3 ,-1 , 0
  4366.4     .05       0    4998     .03       0  5013.4     .05       0
Bank Sta=4998,5013.4
XS Rating Curve= 0 ,0
Exp/Cntr=0.3,0.1

Type RM Length L Ch R = 1 ,4711    ,448,448,448
BEGIN DESCRIPTION:
KEENER BRANCH 9.0
END DESCRIPTION:
XS GIS Cut Line= 3
      2789205.68     10152903.13       2789471.5       10152345.
       2789882.8     10151487.88
#Sta/Elev= 30
  4381.8 1267.23  4554.9 1262.98  4651.2 1259.09  4725.2 1259.41    4847 1258.55
  4923.7 1259.36  4929.2 1258.23  4935.6 1254.01  4951.9 1248.61  4992.1 1246.61
  4992.6 1246.11  5007.9 1246.61    5020 1248.57  5087.9 1253.18  5093.5 1252.86
  5138.8 1257.13  5178.5 1258.97  5302.9 1258.43  5342.6 1259.68  5484.1  1267.5
  5567.8 1270.07  5580.2 1271.68  5619.9 1271.04  5710.5    1272  5800.7 1274.73
    5852 1277.16  5867.3    1277  5880.2 1278.58  5897.3 1277.92  5950.7 1280.33
#Mann= 3 ,-1 , 0
  4381.8     .05       0  4992.1     .05       0  5007.9     .05       0
Bank Sta=4992.1,5007.9
XS Rating Curve= 0 ,0
Exp/Cntr=0.3,0.1

Type RM Length L Ch R = 1 ,4263    ,637,637,637
BEGIN DESCRIPTION:
KEENER BRANCH 8.0
END DESCRIPTION:
XS GIS Cut Line= 3
      2789455.68     10153203.12      2789956.27     10152385.14
       2790132.7     10151707.23
#Sta/Elev= 30
  4274.7 1273.52  4427.1 1263.34  4551.4 1258.53  4667.5 1255.91  4820.1 1256.09
  4899.6 1257.17  4930.5 1254.87  4944.6 1252.17  4986.4  1245.4  4986.9  1244.9
  5002.4  1245.4  5031.2 1247.66  5067.9 1247.42  5095.4 1254.24  5110.5 1255.44
    5126 1255.29  5147.3 1252.54  5177.5 1252.38    5232 1256.86  5318.5 1257.35
  5367.7 1258.57  5372.8 1259.66  5413.3 1259.78  5489.2 1263.75  5680.1 1270.64
  5686.6 1271.99  5691.8 1270.73    5803 1275.37  5808.2 1274.32  5934.2  1277.4
#Mann= 5 ,-1 , 0
  4274.7     .05       0  4820.1     .12       0  4944.6     .05       0
  4986.4     .03       0  5002.4     .05       0
Bank Sta=4986.4,5002.4
XS Rating Curve= 0 ,0
Exp/Cntr=0.3,0.1

Type RM Length L Ch R = 1 ,3626    ,194,194,194
BEGIN DESCRIPTION:
KEENER BRANCH 7.0
END DESCRIPTION:
XS GIS Cut Line= 3
      2789763.12     10153248.03      2790205.85     10153070.94
      2790960.86     10152295.11
#Sta/Elev= 30
  4318.1 1259.24  4400.2    1256  4633.2 1251.31    4664 1251.98  4669.4 1252.91
    4699 1251.94  4771.7 1251.92  4913.5 1253.31  4948.8 1250.15    4956  1247.6
  4997.4 1243.01  4997.9 1242.51  5013.4 1243.01  5026.7 1246.19  5040.9 1246.84
  5069.1 1245.17  5090.3  1245.3  5132.7 1250.27    5161 1247.84  5210.5 1251.98
  5231.7 1251.38    5267 1253.35  5274.2 1251.52  5288.3 1251.09  5345.7 1253.53
  5350.5 1253.68  5705.5 1269.22  5818.7 1268.51  5868.1 1269.33  5877.5 1268.56
#Mann= 5 ,-1 , 0
  4318.1     .05       0  4997.4     .03       0  5013.4     .05       0
  5345.7     .12       0  5350.5     .05       0
Bank Sta=4997.4,5013.4
XS Rating Curve= 0 ,0
Exp/Cntr=0.3,0.1

Type RM Length L Ch R = 1 ,3432    ,692,692,692
BEGIN DESCRIPTION:
KEENER BRANCH 6.0
END DESCRIPTION:
XS GIS Cut Line= 3
      2790205.83     10153289.71       2790737.1     10152810.53
      2791117.32     10152409.47
#Sta/Elev= 30
  4572.3 1251.32  4662.8 1250.45  4676.2 1251.94  4704.6 1250.39    4791 1251.12
    4860 1251.49  4916.8 1249.83  4945.2 1245.23  4951.9 1241.95  4959.4 1242.91
  4986.5 1240.09    4987 1239.59  5002.6 1240.09  5051.3 1241.79  5093.9 1249.63
  5108.1 1250.46  5150.7 1249.93  5242.6 1252.76  5447.8 1263.53  5461.9 1263.98
    5483 1262.51  5553.7 1264.06  5560.6  1263.1  5610.4 1264.32  5631.4 1263.57
  5681.2 1265.28  5702.2 1264.62  5723.6 1266.05    5773 1265.63  5840.4 1267.04
#Mann= 5 ,-1 , 0
  4572.3     .05       0  4662.8     .12       0    4791     .05       0
  4986.5     .05       0  5002.6     .05       0
Bank Sta=4986.5,5002.6
XS Rating Curve= 0 ,0
Exp/Cntr=0.3,0.1

Type RM Length L Ch R = 1 ,2740    ,604,604,604
BEGIN DESCRIPTION:
KEENER BRANCH 5.0
END DESCRIPTION:
XS GIS Cut Line= 3
      2790505.68     10153903.12      2791073.75       10153373.
      2791255.69     10153153.11
#Sta/Elev= 30
    4223 1272.22  4293.6 1265.93  4400.1 1254.51  4526.2 1248.44    4598 1247.56
  4612.1 1249.05  4675.6 1248.22  4711.3 1244.23  4732.3 1235.81  4759.9 1231.18
  4760.4 1230.68    4776 1231.18  4796.3 1235.92  4803.1 1238.94  4817.3 1242.58
  4831.5 1244.69  4845.6 1243.86    4874 1246.94  4916.5 1245.14  4930.6 1243.48
  4951.7 1237.15  4982.9 1235.74  5022.9 1235.22  5043.8 1236.67  5078.9 1236.88
  5107.6  1240.8  5129.6  1241.8  5157.1 1247.76  5193.6 1249.08  5285.4 1256.01
#Mann= 5 ,-1 , 0
    4223     .05       0  4526.2     .12       0  4759.9     .05       0
    4776     .12       0  4982.9     .05       0
Bank Sta=4759.9,4776
XS Rating Curve= 0 ,0
Exp/Cntr=0.3,0.1

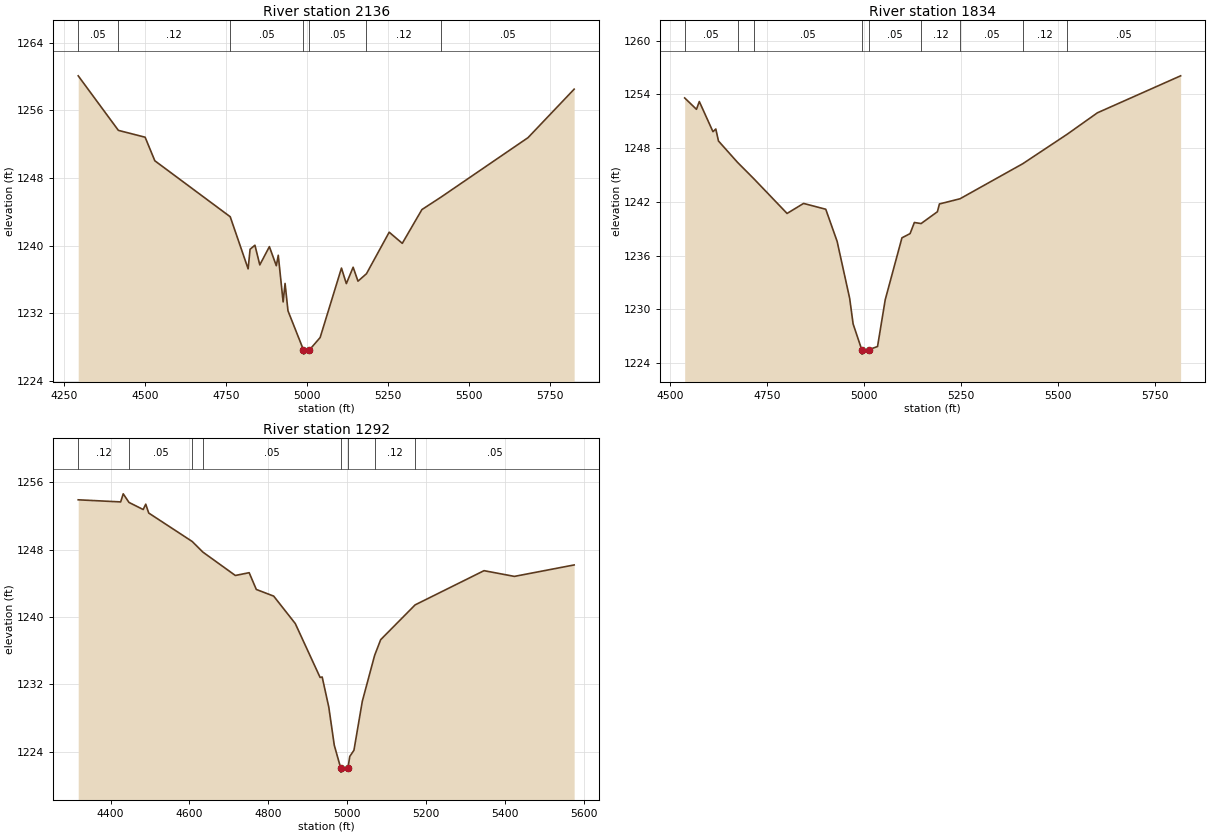
Type RM Length L Ch R = 1 ,2136    ,302,302,302
BEGIN DESCRIPTION:
KEENER BRANCH 4.0
END DESCRIPTION:
XS GIS Cut Line= 3
      2791007.94     10154373.02      2791497.51     10153643.86
      2791591.25      10152998.1
#Sta/Elev= 30
  4294.6  1260.1  4418.6 1253.64  4501.1 1252.83  4531.1 1250.04  4763.8 1243.41
  4819.1 1237.24  4825.1 1239.56  4840.1 1240.04  4855.1 1237.71  4884.7 1239.87
  4906.1 1237.61  4912.1 1238.85  4927.1 1233.32  4933.1 1235.51  4942.1 1232.27
  4989.9 1227.64  4990.4 1227.14  5008.3 1227.64  5041.3  1229.1  5107.2 1237.33
  5122.2 1235.49  5143.2 1237.43  5158.2 1235.78  5184.3 1236.66  5254.5 1241.58
  5294.9 1240.26  5355.5 1244.26  5414.3 1245.73  5683.1 1252.78  5825.4 1258.52
#Mann= 7 ,-1 , 0
  4294.6     .05       0  4418.6     .12       0  4763.8     .05       0
  4989.9     .05       0  5008.3     .05       0  5184.3     .12       0
  5414.3     .05       0
Bank Sta=4989.9,5008.3
XS Rating Curve= 0 ,0
Exp/Cntr=0.3,0.1

Type RM Length L Ch R = 1 ,1834    ,542,542,542
BEGIN DESCRIPTION:
KEENER BRANCH 3.0
END DESCRIPTION:
XS GIS Cut Line= 3
      2791393.38     10154274.04      2791642.45     10154012.54
      2791919.37      10153138.7
#Sta/Elev= 30
  4537.1  1253.6  4567.5 1252.33  4574.8  1253.2    4610 1249.83  4617.3 1250.13
  4624.2 1248.79  4673.2 1246.41  4715.9 1244.55  4800.9  1240.7  4843.4 1241.82
  4900.6 1241.17  4929.9 1237.58  4962.2 1231.22  4971.1 1228.36  4993.3 1225.49
  4993.8 1224.99  5011.8 1225.49    5034 1225.84  5053.8 1231.06  5096.9 1237.98
  5117.9 1238.45  5128.9 1239.69  5146.2 1239.57  5188.2 1240.89  5193.5 1241.76
  5246.5 1242.34  5408.4 1246.26  5522.1 1249.53  5600.5 1251.94  5814.9 1256.07
#Mann= 9 ,-1 , 0
  4537.1     .05       0  4673.2     .12       0  4715.9     .05       0
  4993.3     .05       0  5011.8     .05       0  5146.2     .12       0
  5246.5     .05       0  5408.4     .12       0  5522.1     .05       0
Bank Sta=4993.3,5011.8
XS Rating Curve= 0 ,0
Exp/Cntr=0.3,0.1

Type RM Length L Ch R = 1 ,1292    ,0,0,0
BEGIN DESCRIPTION:
KEENER BRANCH 2.0
END DESCRIPTION:
XS GIS Cut Line= 4
      2791809.99     10154649.09      2792105.68     10154303.11
      2792293.33     10153780.23      2792190.21      10153555.3
#Sta/Elev= 30
    4318  1253.9  4425.7 1253.65  4432.2 1254.61  4446.8 1253.59  4482.8 1252.75
  4489.3 1253.38  4496.9 1252.33  4607.3 1248.95  4634.1  1247.7  4716.6 1244.92
  4751.7 1245.25  4769.8 1243.26  4813.9 1242.47  4868.7 1239.21  4931.6 1232.82
  4936.9 1232.87  4953.7 1229.29  4967.6 1224.77  4983.8 1222.08  4984.3 1221.58
  5002.3 1222.08  5006.9 1223.44  5017.5 1224.18  5038.7 1229.99  5069.9 1235.43
  5085.3  1237.3  5172.7 1241.43  5347.5 1245.49  5424.5 1244.81  5576.1 1246.17
#Mann= 8 ,-1 , 0
    4318     .12       0  4446.8     .05       0  4607.3     .12       0
  4634.1     .05       0  4983.8     .03       0  5002.3     .05       0
  5069.9     .12       0  5172.7     .05       0
Bank Sta=4983.8,5002.3
XS Rating Curve= 0 ,0
Exp/Cntr=0.3,0.1

Chan Stop Cuts=-1
Use User Specified Reach Order=0
Composite Channel Slope=5