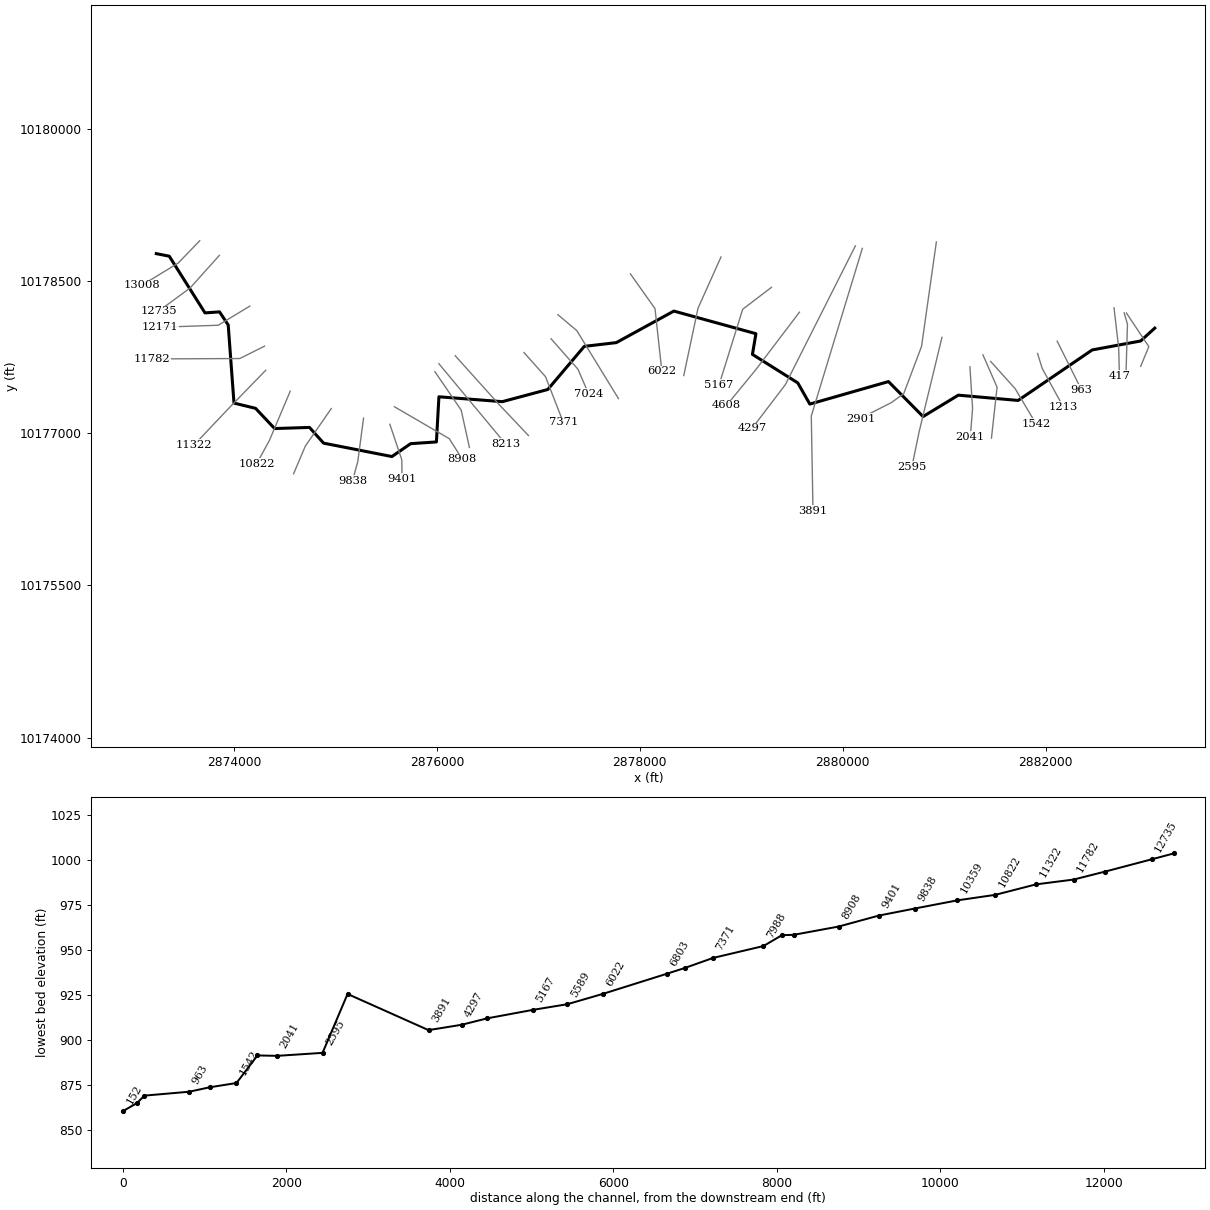
--- LIME HOLLOW CREEK.prj (project) ---

Proj Title=LIME HOLLOW CREEK Base Level Engineering
Current Plan=p01
Default Exp/Contr=0.3,0.1
English Units
Geom File=g01
Flow File=f01
Plan File=p01
BEGIN DESCRIPTION:
LIME HOLLOW CREEK
END DESCRIPTION:

--- LIME HOLLOW CREEK.p01 (plan) ---

Plan Title=Multiple Run
Short Identifier=Multiple
Geom File=g01
Flow File=f01
Subcritical Flow
K Sum by GR= 0
Std Step Tol= 0.01
Critical Tol= 0.01
Num of Std Step Trials= 20
Max Error Tol= 0.3
Flow Tol Ratio= 0.001
Split Flow NTrial= 30
Split Flow Tol= 0.02
Split Flow Ratio= 0.02
Log Output Level= 0
Friction Slope Method= 1
Unsteady Friction Slope Method= 2
Unsteady Bridges Friction Slope Method= 1
Parabolic Critical Depth
Global Vel Dist=  1 , 1 , 1
Global Log Level= 0
CheckData=True
Encroach Param= -1, 0, 0, 0
BEGIN DESCRIPTION:
Multiple Run
END DESCRIPTION:

--- LIME HOLLOW CREEK.f01 (steady flow) ---

Flow Title=Multiple
Number of Profiles=7
Profile Names=10-year,25-year,50-year,1pct_min,100-year,1pct_plu,500-year
River Rch & RM= LIME HOLLOW CREE,Reach-1,13008
     469     766     968     696    1287    2380    1764
River Rch & RM= LIME HOLLOW CREE,Reach-1,2901
     639    1065    1473    1048    1999    3811    2761
River Rch & RM= LIME HOLLOW CREE,Reach-1,152
    1660    2931    4274    2923    5970   12195    8137
Boundary for River Rch & Prof#=LIME HOLLOW CREE,Reach-1,1
Up Type=0
Dn Type=3
Dn Slope=0.005
Boundary for River Rch & Prof#=LIME HOLLOW CREE,Reach-1,2
Up Type=0
Dn Type=3
Dn Slope=0.005
Boundary for River Rch & Prof#=LIME HOLLOW CREE,Reach-1,3
Up Type=0
Dn Type=3
Dn Slope=0.005
Boundary for River Rch & Prof#=LIME HOLLOW CREE,Reach-1,4
Up Type=0
Dn Type=3
Dn Slope=0.005
Boundary for River Rch & Prof#=LIME HOLLOW CREE,Reach-1,5
Up Type=0
Dn Type=3
Dn Slope=0.005
Boundary for River Rch & Prof#=LIME HOLLOW CREE,Reach-1,6
Up Type=0
Dn Type=3
Dn Slope=0.005
Boundary for River Rch & Prof#=LIME HOLLOW CREE,Reach-1,7
Up Type=0
Dn Type=3
Dn Slope=0.005

--- LIME HOLLOW CREEK.g01 (geometry) ---

Geom Title=Existing Conditions

River Reach=LIME HOLLOW CREE,Reach-1
Reach XY= 30
      2873233.75     10178770.00      2873361.25     10178745.00
      2873713.75     10178186.00      2873857.00     10178196.00
      2873942.50     10178067.00      2873999.50     10177297.00
      2874212.50     10177245.00      2874400.00     10177046.00
      2874743.75     10177057.00      2874882.75     10176902.00
      2875556.25     10176770.00      2875741.25     10176897.00
      2875995.00     10176914.00      2876019.75     10177359.00
      2876644.50     10177311.00      2877093.00     10177431.00
      2877452.75     10177856.00      2877768.50     10177893.00
      2878336.00     10178204.00      2879145.00     10177981.00
      2879110.50     10177777.00      2879557.50     10177496.00
      2879676.25     10177287.00      2880451.75     10177509.00
      2880792.75     10177164.00      2881140.00     10177375.00
      2881729.75     10177323.00      2882460.50     10177821.00
      2882937.50     10177909.00      2883077.00     10178036.00

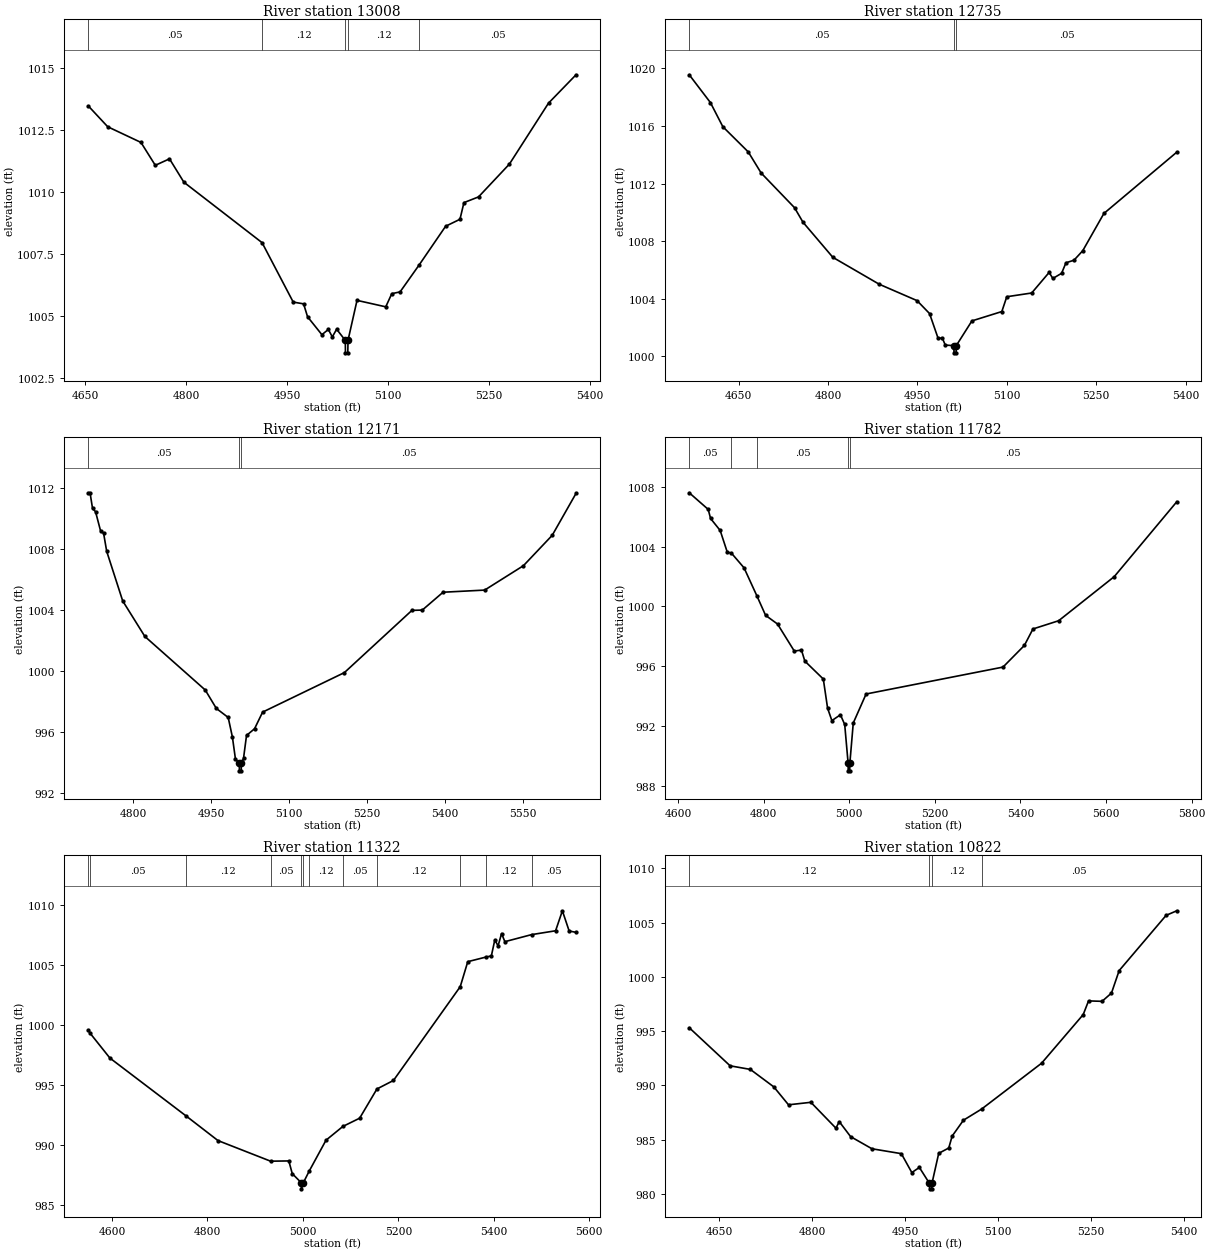
Type RM Length L Ch R = 1,13008,273,273,273
BEGIN DESCRIPTION:
LIME HOLLOW CREEK 27.0
END DESCRIPTION:
XS GIS Cut Line= 3
      2873661.77     10178897.36      2873449.54     10178677.27
      2873091.95     10178459.18
#Sta/Elev= 30
  4655.0 1013.45  4683.6 1012.62  4733.0 1011.99  4754.3 1011.07  4775.4 1011.33
  4796.8 1010.39  4913.0 1007.96  4959.3 1005.57  4974.7 1005.50  4980.6 1004.98
  5001.9 1004.26  5011.5 1004.47  5017.4 1004.17  5023.8 1004.48  5036.7 1004.03
  5036.9 1003.53  5040.4 1003.53  5040.7 1004.03  5054.1 1005.64  5096.8 1005.38
  5105.8 1005.91  5118.1 1005.98  5146.6 1007.07  5185.8 1008.62  5207.1 1008.90
  5213.0 1009.57  5234.7 1009.80  5280.6 1011.12  5338.7 1013.57  5379.6 1014.71
#Mann=5,-1,0
  4655.0    0.05       0  4913.0    0.12       0  5036.7    0.07       0
  5040.7    0.12       0  5146.6    0.05       0
Bank Sta=5036.7,5040.7
Exp/Cntr=0.3,0.1

Type RM Length L Ch R = 1,12735,564,564,564
BEGIN DESCRIPTION:
LIME HOLLOW CREEK 26.0
END DESCRIPTION:
XS GIS Cut Line= 3
      2873855.65     10178753.08      2873566.25     10178431.00
      2873255.69     10178203.12
#Sta/Elev= 30
  4567.0 1019.56  4602.5 1017.63  4623.4 1015.95  4666.0 1014.20  4687.7 1012.73
  4743.7 1010.32  4757.9 1009.31  4808.0 1006.87  4885.8 1005.00  4949.3 1003.86
  4970.3 1002.96  4984.4 1001.27  4991.9 1001.24  4996.7 1000.77  5011.1 1000.73
  5011.4 1000.23  5014.9 1000.23  5015.1 1000.73  5041.4 1002.45  5091.6 1003.10
  5099.9 1004.13  5141.7 1004.39  5171.0 1005.82  5177.2 1005.40  5191.9 1005.76
  5199.2 1006.49  5212.7 1006.67  5227.4 1007.33  5262.9 1009.92  5385.2 1014.18
#Mann=3,-1,0
  4567.0    0.05       0  5011.1    0.05       0  5015.1    0.05       0
Bank Sta=5011.1,5015.1
Exp/Cntr=0.3,0.1

Type RM Length L Ch R = 1,12171,389,389,389
BEGIN DESCRIPTION:
LIME HOLLOW CREEK 25.0
END DESCRIPTION:
XS GIS Cut Line= 3
      2874155.72     10178253.13      2873844.46     10178064.26
      2873269.78     10178044.64
#Sta/Elev= 30
  4713.4 1011.70  4716.4 1011.70  4721.2 1010.68  4727.0 1010.46  4736.7 1009.20
  4742.5 1009.05  4748.5 1007.86  4779.3 1004.61  4822.0 1002.28  4938.3  998.77
  4959.7  997.56  4982.5  996.97  4990.6  995.69  4996.5  994.24  5003.9  993.97
  5004.1  993.47  5007.6  993.47  5007.9  993.97  5012.0  994.28  5017.8  995.79
  5033.3  996.23  5048.8  997.32  5206.3  999.91  5336.4 1003.99  5356.4 1004.01
  5396.4 1005.18  5476.5 1005.32  5551.2 1006.92  5606.6 1008.91  5652.5 1011.66
#Mann=3,-1,0
  4713.4    0.05       0  5003.9    0.05       0  5007.9    0.05       0
Bank Sta=5003.9,5007.9
Exp/Cntr=0.3,0.1

Type RM Length L Ch R = 1,11782,460,460,460
BEGIN DESCRIPTION:
LIME HOLLOW CREEK 24.0
END DESCRIPTION:
XS GIS Cut Line= 3
      2874300.29     10177857.95      2874056.66     10177736.14
      2873189.46     10177732.21
#Sta/Elev= 30
  4625.7 1007.60  4670.0 1006.49  4675.6 1005.88  4698.0 1005.08  4714.7 1003.62
  4724.1 1003.57  4753.8 1002.58  4783.9 1000.70  4804.2  999.40  4832.1  998.82
  4871.3  997.01  4888.0  997.08  4895.9  996.34  4939.1  995.14  4949.1  993.19
  4959.1  992.36  4979.1  992.75  4989.1  992.10  4997.1  989.50  4997.3  989.00
  5000.8  989.00  5001.1  989.50  5009.1  992.20  5039.1  994.14  5359.1  995.94
  5409.1  997.39  5429.1  998.49  5489.1  999.04  5619.1 1001.99  5765.3 1007.00
#Mann=5,-1,0
  4625.7    0.05       0  4724.1    0.12       0  4783.9    0.05       0
  4997.1    0.03       0  5001.1    0.05       0
Bank Sta=4997.1,5001.1
Exp/Cntr=0.3,0.1

Type RM Length L Ch R = 1,11322,500,500,500
BEGIN DESCRIPTION:
LIME HOLLOW CREEK 23.0
END DESCRIPTION:
XS GIS Cut Line= 3
      2874312.09     10177620.22      2873951.05     10177248.70
      2873604.75     10176883.41
#Sta/Elev= 30
  4550.9  999.57  4553.6  999.35  4595.8  997.24  4755.6  992.40  4822.2  990.35
  4932.4  988.63  4970.6  988.65  4977.8  987.59  4996.9  986.82  4997.1  986.32
  5000.9  986.82  5013.4  987.81  5048.5  990.38  5083.8  991.53  5119.0  992.22
  5155.2  994.66  5189.8  995.37  5329.7 1003.20  5345.5 1005.29  5384.1 1005.68
  5394.9 1005.77  5402.1 1007.10  5409.0 1006.61  5416.3 1007.64  5423.2 1006.96
  5479.3 1007.55  5529.5 1007.87  5543.7 1009.54  5557.9 1007.85  5572.3 1007.74
#Mann=12,-1,0
  4550.9    0.12       0  4553.6    0.05       0  4755.6    0.12       0
  4932.4    0.05       0  4996.9    0.05       0  5000.9    0.05       0
  5013.4    0.12       0  5083.8    0.05       0  5155.2    0.12       0
  5329.7    0.05       0  5384.1    0.12       0  5479.3    0.05       0
Bank Sta=4996.9,5000.9
Exp/Cntr=0.3,0.1

Type RM Length L Ch R = 1,10822,463,463,463
BEGIN DESCRIPTION:
LIME HOLLOW CREEK 22.0
END DESCRIPTION:
XS GIS Cut Line= 3
      2874553.76     10177413.94      2874348.65     10176928.83
      2874223.68     10176700.71
#Sta/Elev= 30
  4601.8  995.32  4667.8  991.81  4700.4  991.48  4738.3  989.87  4762.0  988.22
  4798.1  988.45  4838.5  986.07  4843.9  986.67  4862.2  985.29  4896.7  984.17
  4944.1  983.72  4961.0  981.98  4973.2  982.45  4989.5  980.98  4989.8  980.48
  4993.3  980.48  4993.5  980.98  5004.4  983.75  5020.6  984.24  5026.1  985.34
  5044.3  986.80  5073.7  987.83  5170.4  992.05  5237.6  996.53  5246.2  997.79
  5268.0  997.75  5283.2  998.51  5295.6 1000.58  5371.4 1005.67  5388.6 1006.09
#Mann=4,-1,0
  4601.8    0.12       0  4989.5    0.07       0  4993.5    0.12       0
  5073.7    0.05       0
Bank Sta=4989.5,4993.5
Exp/Cntr=0.3,0.1

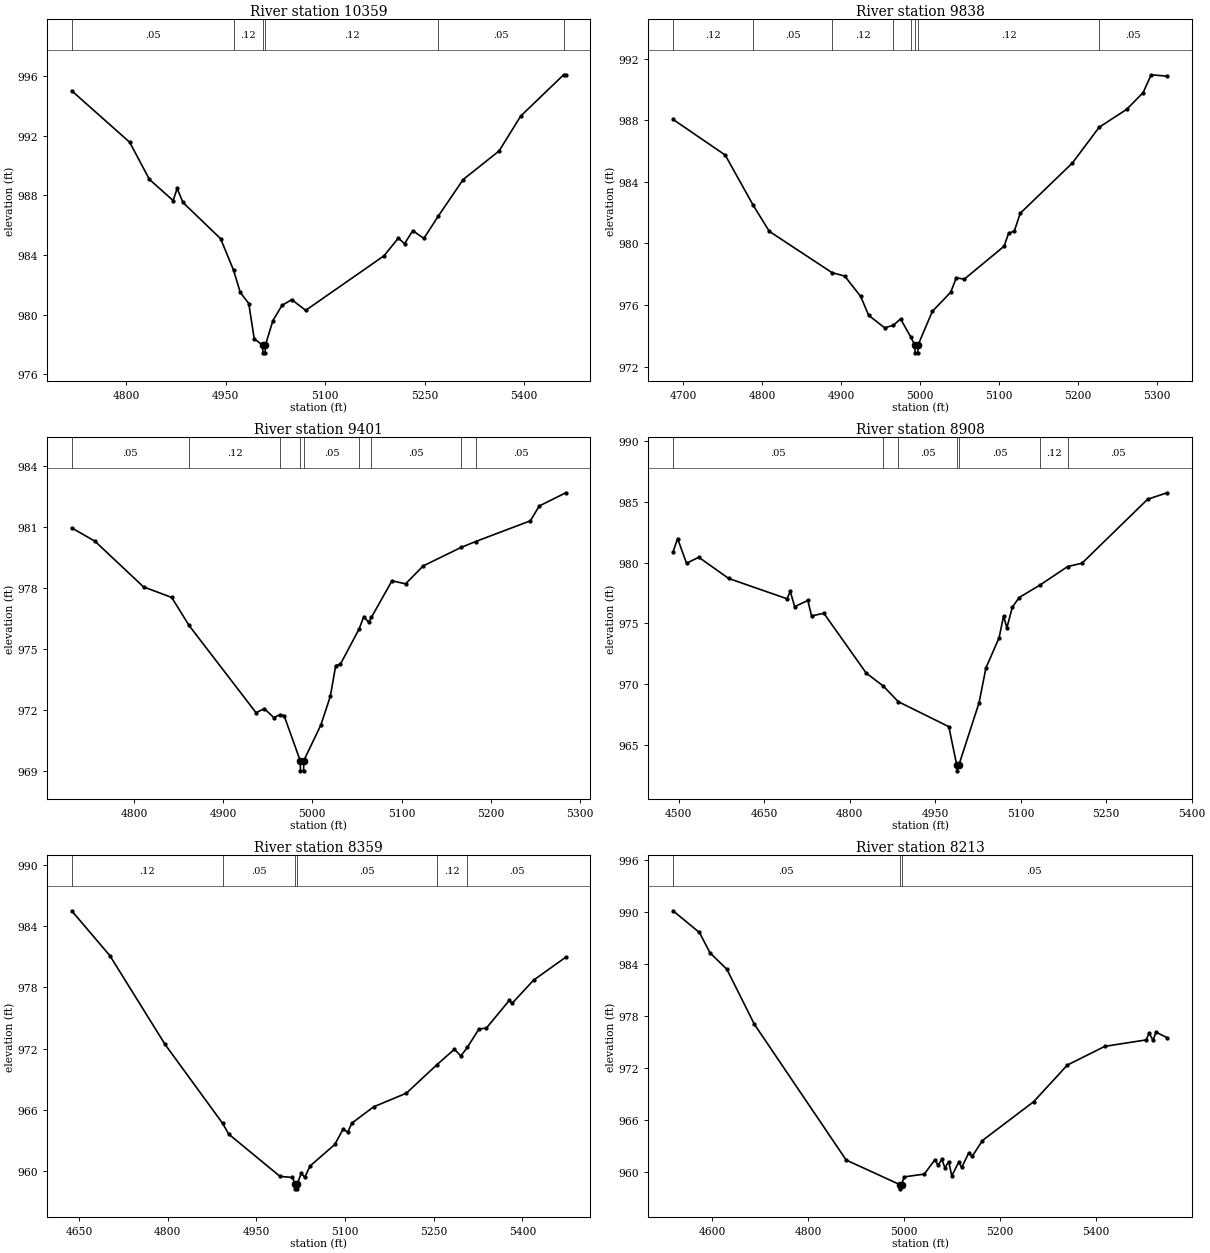
Type RM Length L Ch R = 1,10359,521,521,521
BEGIN DESCRIPTION:
LIME HOLLOW CREEK 21.0
END DESCRIPTION:
XS GIS Cut Line= 3
      2874958.51     10177243.00      2874703.07     10176873.60
      2874587.16     10176600.50
#Sta/Elev= 30
  4717.4  995.02  4805.0  991.56  4834.7  989.07  4870.5  987.65  4876.6  988.46
  4885.4  987.52  4942.2  985.09  4961.7  982.98  4971.9  981.48  4984.7  980.74
  4992.9  978.38  5005.7  977.93  5006.0  977.43  5009.5  977.43  5009.7  977.93
  5021.2  979.60  5034.8  980.61  5049.6  981.00  5070.6  980.28  5188.8  983.94
  5210.5  985.13  5219.9  984.75  5232.2  985.63  5249.0  985.11  5270.7  986.60
  5308.3  989.06  5362.6  990.98  5395.2  993.32  5460.0  996.09  5463.2  996.09
#Mann=6,-1,0
  4717.4    0.05       0  4961.7    0.12       0  5005.7    0.07       0
  5009.7    0.12       0  5270.7    0.05       0  5460.0    0.12       0
Bank Sta=5005.7,5009.7
Exp/Cntr=0.3,0.1

Type RM Length L Ch R = 1,9838,437,437,437
BEGIN DESCRIPTION:
LIME HOLLOW CREEK 20.0
END DESCRIPTION:
XS GIS Cut Line= 3
      2875276.79     10177148.66      2875219.81     10176720.35
      2875168.73     10176533.70
#Sta/Elev= 30
  4687.0  988.07  4753.1  985.75  4788.5  982.49  4808.9  980.79  4888.2  978.11
  4904.4  977.88  4924.6  976.56  4934.7  975.33  4954.9  974.52  4966.1  974.68
  4975.1  975.10  4987.9  973.93  4993.2  973.39  4993.5  972.89  4997.0  972.89
  4997.2  973.39  5015.4  975.59  5038.6  976.83  5045.7  977.77  5055.8  977.68
  5106.2  979.82  5111.9  980.67  5119.1  980.80  5126.6  981.96  5192.8  985.24
  5226.6  987.56  5261.4  988.72  5282.1  989.80  5292.5  990.97  5312.6  990.88
#Mann=8,-1,0
  4687.0    0.12       0  4788.5    0.05       0  4888.2    0.12       0
  4966.1    0.05       0  4987.9    0.12       0  4993.2    0.07       0
  4997.2    0.12       0  5226.6    0.05       0
Bank Sta=4993.2,4997.2
Exp/Cntr=0.3,0.1

Type RM Length L Ch R = 1,9401,493,493,493
BEGIN DESCRIPTION:
LIME HOLLOW CREEK 19.0
END DESCRIPTION:
XS GIS Cut Line= 3
      2875536.13     10177087.79      2875653.90     10176737.51
      2875655.99     10176553.37
#Sta/Elev= 30
  4730.3  980.94  4756.3  980.29  4810.8  978.04  4842.4  977.52  4861.7  976.15
  4936.9  971.85  4946.2  972.05  4956.8  971.61  4964.0  971.76  4968.4  971.70
  4986.4  969.49  4986.7  968.99  4990.2  968.99  4990.4  969.49  5009.5  971.24
  5020.1  972.65  5026.2  974.17  5031.5  974.24  5052.3  975.96  5057.7  976.58
  5063.0  976.30  5066.2  976.54  5089.2  978.34  5104.5  978.19  5124.2  979.07
  5166.6  979.98  5182.9  980.27  5244.3  981.29  5254.3  982.02  5284.0  982.67
#Mann=9,-1,0
  4730.3    0.05       0  4861.7    0.12       0  4964.0    0.05       0
  4986.4    0.05       0  4990.4    0.05       0  5052.3    0.12       0
  5066.2    0.05       0  5166.6    0.12       0  5182.9    0.05       0
Bank Sta=4986.4,4990.4
Exp/Cntr=0.3,0.1

Type RM Length L Ch R = 1,8908,549,549,549
BEGIN DESCRIPTION:
LIME HOLLOW CREEK 18.0
END DESCRIPTION:
XS GIS Cut Line= 3
      2875581.32     10177260.67      2876121.65     10176946.30
      2876250.98     10176742.49
#Sta/Elev= 30
  4490.3  980.86  4498.3  981.97  4514.0  979.94  4535.5  980.43  4587.9  978.69
  4690.2  977.02  4696.0  977.62  4703.6  976.37  4726.7  976.88  4733.3  975.61
  4754.8  975.83  4829.2  970.91  4859.0  969.85  4885.5  968.56  4974.0  966.51
  4987.8  963.38  4988.0  962.88  4991.8  963.38  5027.0  968.47  5039.1  971.34
  5062.2  973.82  5070.0  975.60  5075.8  974.63  5085.4  976.33  5097.3  977.12
  5133.6  978.14  5182.5  979.67  5207.5  979.94  5322.7  985.20  5356.8  985.73
#Mann=7,-1,0
  4490.3    0.05       0  4859.0    0.12       0  4885.5    0.05       0
  4987.8    0.05       0  4991.8    0.05       0  5133.6    0.12       0
  5182.5    0.05       0
Bank Sta=4987.8,4991.8
Exp/Cntr=0.3,0.1

Type RM Length L Ch R = 1,8359,146,146,146
BEGIN DESCRIPTION:
LIME HOLLOW CREEK 17.0
END DESCRIPTION:
XS GIS Cut Line= 3
      2875980.16     10177606.50      2876239.54     10177227.26
      2876320.09     10176859.84
#Sta/Elev= 30
  4637.8  985.48  4702.5  981.08  4795.7  972.41  4893.0  964.69  4903.4  963.63
  4990.1  959.50  5011.1  959.39  5015.5  958.78  5015.7  958.28  5019.2  958.28
  5019.5  958.78  5026.0  959.80  5032.0  959.41  5040.9  960.51  5082.8  962.62
  5096.7  964.11  5104.6  963.83  5111.7  964.71  5148.4  966.30  5203.9  967.64
  5255.6  970.43  5285.0  971.93  5296.0  971.28  5306.9  972.12  5326.7  973.92
  5339.1  974.00  5377.8  976.71  5382.9  976.44  5418.9  978.69  5473.4  980.94
#Mann=6,-1,0
  4637.8    0.12       0  4893.0    0.05       0  5015.5    0.05       0
  5019.5    0.05       0  5255.6    0.12       0  5306.9    0.05       0
Bank Sta=5015.5,5019.5
Exp/Cntr=0.3,0.1

Type RM Length L Ch R = 1,8213,225,225,225
BEGIN DESCRIPTION:
Mapping XS b5fe4881
END DESCRIPTION:
XS GIS Cut Line= 2
      2876019.46     10177685.08      2876677.69     10176893.24
#Sta/Elev= 30
  4518.1  990.12  4573.1  987.62  4595.2  985.27  4630.4  983.37  4687.6  977.04
  4879.0  961.38  4990.3  958.56  4990.6  958.06  4994.3  958.56  5000.1  959.44
  5041.8  959.76  5063.9  961.42  5070.4  960.77  5078.2  961.46  5084.8  960.48
  5092.6  961.20  5099.1  959.55  5113.4  961.12  5119.9  960.54  5134.2  962.18
  5142.0  961.83  5162.9  963.63  5269.6  968.10  5339.9  972.33  5418.1  974.49
  5504.0  975.23  5510.5  976.02  5518.3  975.19  5524.8  976.12  5547.8  975.49
#Mann=3,-1,0
  4518.1    0.05       0  4990.3    0.03       0  4994.3    0.05       0
Bank Sta=4990.3,4994.3
Exp/Cntr=0.3,0.1

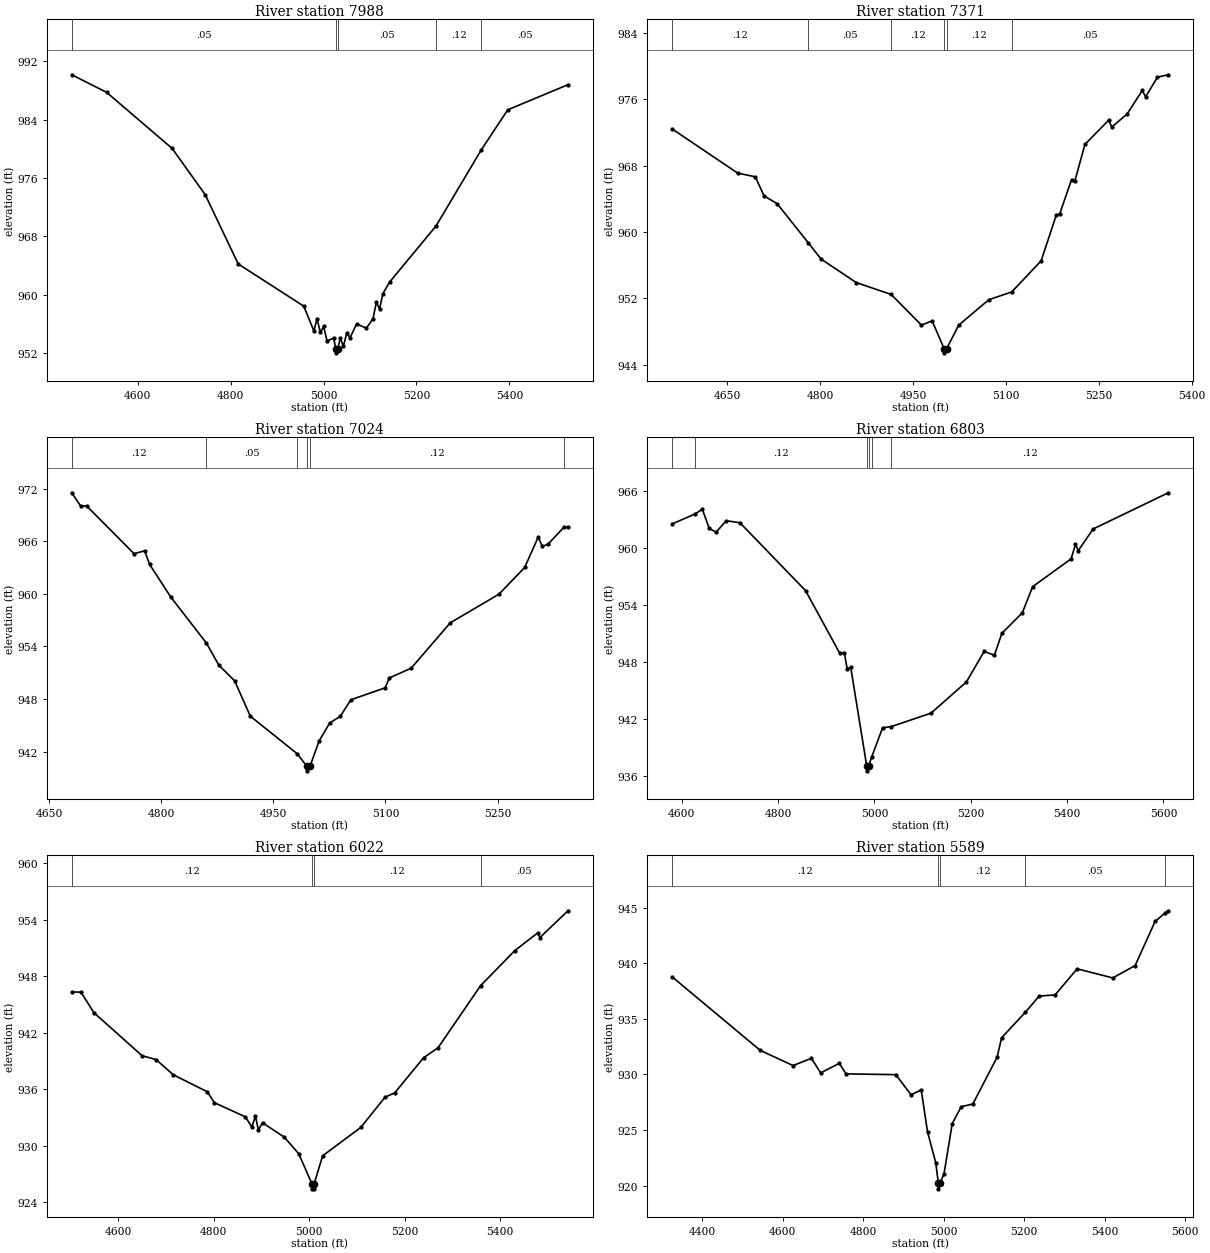
Type RM Length L Ch R = 1,7988,617,617,617
BEGIN DESCRIPTION:
LIME HOLLOW CREEK 16.0
END DESCRIPTION:
XS GIS Cut Line= 3
      2876180.62     10177763.62      2876608.87     10177287.27
      2876902.53     10176976.94
#Sta/Elev= 30
  4458.3  990.13  4533.1  987.73  4674.3  980.04  4745.3  973.72  4816.4  964.22
  4957.6  958.43  4979.3  955.04  4986.0  956.69  4993.5  954.83  5000.2  955.66
  5007.7  953.65  5021.9  954.07  5026.6  952.54  5026.9  952.04  5030.6  952.54
  5036.1  954.06  5042.8  952.93  5050.3  954.81  5057.0  954.09  5071.2  955.99
  5092.2  955.42  5106.5  956.70  5113.8  958.99  5120.6  958.04  5127.9  960.16
  5142.1  961.72  5242.4  969.44  5339.4  979.83  5396.5  985.33  5526.1  988.77
#Mann=5,-1,0
  4458.3    0.05       0  5026.6    0.03       0  5030.6    0.05       0
  5242.4    0.12       0  5339.4    0.05       0
Bank Sta=5026.6,5030.6
Exp/Cntr=0.3,0.1

Type RM Length L Ch R = 1,7371,347,347,347
BEGIN DESCRIPTION:
LIME HOLLOW CREEK 15.0
END DESCRIPTION:
XS GIS Cut Line= 3
      2876858.43     10177795.09      2877070.64     10177557.34
      2877245.36     10177107.78
#Sta/Elev= 30
  4561.1  972.44  4666.9  967.11  4695.4  966.66  4709.6  964.36  4730.5  963.43
  4780.7  958.73  4801.5  956.74  4858.4  953.90  4914.9  952.46  4963.7  948.76
  4980.9  949.28  5000.3  945.92  5000.6  945.42  5004.3  945.92  5023.8  948.76
  5072.6  951.84  5109.3  952.76  5156.9  956.52  5181.5  962.08  5186.8  962.17
  5206.0  966.32  5211.4  966.17  5227.6  970.57  5265.8  973.48  5271.1  972.68
  5295.7  974.24  5320.2  977.08  5325.6  976.31  5344.7  978.69  5362.1  978.97
#Mann=6,-1,0
  4561.1    0.12       0  4780.7    0.05       0  4914.9    0.12       0
  5000.3    0.07       0  5004.3    0.12       0  5109.3    0.05       0
Bank Sta=5000.3,5004.3
Exp/Cntr=0.3,0.1

Type RM Length L Ch R = 1,7024,221,221,221
BEGIN DESCRIPTION:
LIME HOLLOW CREEK 14.0
END DESCRIPTION:
XS GIS Cut Line= 3
      2877125.65     10177930.65      2877390.90     10177630.04
      2877495.05     10177388.33
#Sta/Elev= 30
  4680.2  971.54  4692.4  969.99  4699.9  970.06  4763.5  964.59  4777.7  964.92
  4784.4  963.36  4812.8  959.63  4860.3  954.40  4877.0  951.87  4898.2  950.08
  4919.1  946.05  4982.2  941.74  4995.0  940.31  4995.2  939.81  4999.0  940.31
  5011.1  943.20  5025.3  945.26  5039.6  946.04  5053.8  947.92  5099.5  949.28
  5105.4  950.42  5134.4  951.52  5186.9  956.71  5252.0  959.97  5286.4  963.02
  5304.5  966.49  5309.9  965.44  5317.3  965.64  5338.9  967.61  5344.3  967.62
#Mann=6,-1,0
  4680.2    0.12       0  4860.3    0.05       0  4982.2    0.12       0
  4995.0    0.07       0  4999.0    0.12       0  5338.9    0.05       0
Bank Sta=4995,4999
Exp/Cntr=0.3,0.1

Type RM Length L Ch R = 1,6803,781,781,781
BEGIN DESCRIPTION:
LIME HOLLOW CREEK 13.0
END DESCRIPTION:
XS GIS Cut Line= 3
      2877192.45     10178168.40      2877379.11     10178011.21
      2877789.72     10177341.26
#Sta/Elev= 30
  4580.1  962.56  4628.2  963.62  4642.9  964.11  4657.2  962.10  4671.5  961.69
  4692.3  962.90  4720.9  962.69  4857.1  955.55  4928.1  948.96  4937.6  949.00
  4943.5  947.32  4950.9  947.48  4984.1  937.09  4984.3  936.59  4988.1  937.09
  4994.3  938.04  5017.0  941.11  5035.4  941.25  5117.6  942.66  5191.0  945.94
  5227.8  949.15  5249.1  948.75  5264.5  951.05  5307.1  953.22  5328.4  955.96
  5408.3  958.89  5417.3  960.40  5423.2  959.76  5454.0  962.03  5609.9  965.84
#Mann=6,-1,0
  4580.1    0.05       0  4628.2    0.12       0  4984.1    0.05       0
  4988.1    0.12       0  4994.3    0.05       0  5035.4    0.12       0
Bank Sta=4984.1,4988.1
Exp/Cntr=0.3,0.1

Type RM Length L Ch R = 1,6022,433,433,433
BEGIN DESCRIPTION:
LIME HOLLOW CREEK 12.0
END DESCRIPTION:
XS GIS Cut Line= 3
      2877907.41     10178570.80      2878150.07     10178228.17
      2878217.34     10177612.39
#Sta/Elev= 30
  4502.9  946.33  4522.2  946.31  4549.2  944.13  4650.1  939.56  4679.7  939.14
  4715.3  937.54  4786.7  935.73  4801.5  934.57  4866.7  933.06  4879.9  932.00
  4887.6  933.13  4893.8  931.67  4902.4  932.44  4948.0  930.91  4978.1  929.16
  5006.3  925.92  5006.6  925.42  5010.1  925.42  5010.3  925.92  5028.4  928.93
  5108.2  931.94  5159.2  935.16  5179.3  935.61  5239.7  939.34  5269.9  940.39
  5359.1  946.99  5430.8  950.72  5478.5  952.59  5483.5  952.11  5542.2  954.95
#Mann=4,-1,0
  4502.9    0.12       0  5006.3    0.07       0  5010.3    0.12       0
  5359.1    0.05       0
Bank Sta=5006.3,5010.3
Exp/Cntr=0.3,0.1

Type RM Length L Ch R = 1,5589,422,422,422
BEGIN DESCRIPTION:
LIME HOLLOW CREEK 11.0
END DESCRIPTION:
XS GIS Cut Line= 3
      2878800.66     10178737.40      2878574.11     10178232.22
      2878433.49     10177568.20
#Sta/Elev= 30
  4325.2  938.77  4544.3  932.15  4625.8  930.79  4671.2  931.44  4694.4  930.13
  4740.7  930.99  4757.3  930.04  4881.0  929.97  4918.8  928.16  4944.0  928.60
  4959.7  924.82  4980.2  922.03  4986.6  920.20  4986.8  919.70  4990.6  920.20
  5000.6  921.04  5021.0  925.56  5043.4  927.09  5072.2  927.33  5132.5  931.54
  5143.7  933.29  5202.9  935.59  5237.0  937.04  5276.5  937.14  5331.3  939.49
  5419.7  938.67  5475.3  939.78  5524.9  943.75  5549.0  944.48  5557.6  944.71
#Mann=5,-1,0
  4325.2    0.12       0  4986.6    0.07       0  4990.6    0.12       0
  5202.9    0.05       0  5549.0    0.12       0
Bank Sta=4986.6,4990.6
Exp/Cntr=0.3,0.1

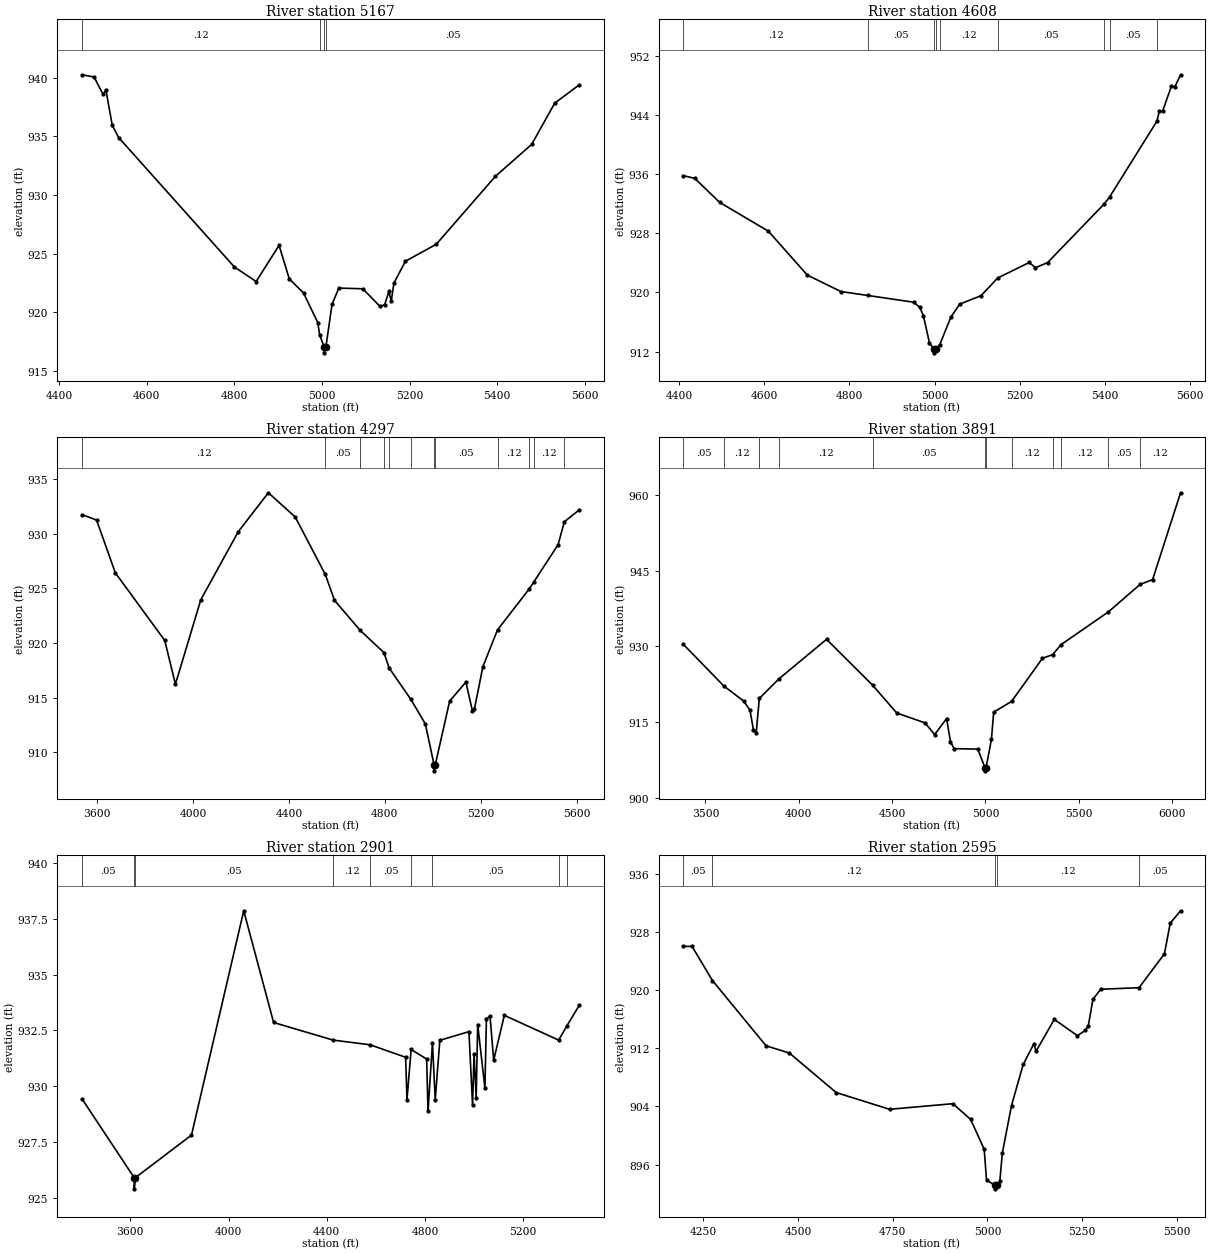
Type RM Length L Ch R = 1,5167,559,559,559
BEGIN DESCRIPTION:
LIME HOLLOW CREEK 10.0
END DESCRIPTION:
XS GIS Cut Line= 3
      2879298.05     10178437.94      2879014.49     10178221.75
      2878782.45     10177479.65
#Sta/Elev= 30
  4453.0  940.25  4480.3  940.06  4501.1  938.57  4507.4  938.96  4521.9  935.93
  4536.4  934.90  4800.4  923.87  4850.1  922.63  4902.4  925.71  4925.7  922.85
  4958.2  921.65  4990.7  919.13  4994.9  918.09  5005.2  917.05  5005.5  916.55
  5009.2  917.05  5023.2  920.68  5038.6  922.07  5093.3  922.01  5132.9  920.50
  5143.4  920.66  5153.0  921.78  5158.3  920.96  5164.4  922.50  5190.7  924.36
  5260.9  925.80  5396.0  931.60  5478.7  934.32  5531.2  937.83  5587.1  939.39
#Mann=4,-1,0
  4453.0    0.12       0  4994.9    0.05       0  5005.2    0.05       0
  5009.2    0.05       0
Bank Sta=5005.2,5009.2
Exp/Cntr=0.3,0.1

Type RM Length L Ch R = 1,4608,311,311,311
BEGIN DESCRIPTION:
LIME HOLLOW CREEK 9.0
END DESCRIPTION:
XS GIS Cut Line= 3
      2879574.09     10178193.14      2879144.74     10177627.53
      2878855.33     10177273.86
#Sta/Elev= 30
  4410.3  935.78  4437.1  935.41  4495.3  932.17  4609.7  928.28  4701.2  922.34
  4780.2  920.12  4843.4  919.59  4950.8  918.68  4965.4  917.97  4973.6  916.86
  4987.9  913.18  4998.7  912.34  4999.0  911.84  5002.7  912.34  5011.8  912.90
  5038.1  916.66  5058.9  918.42  5108.9  919.56  5148.1  921.95  5222.3  924.05
  5236.6  923.34  5265.4  924.04  5398.8  932.00  5411.3  932.94  5521.8  943.13
  5527.4  944.47  5535.3  944.51  5556.1  947.90  5564.0  947.79  5577.4  949.41
#Mann=9,-1,0
  4410.3    0.12       0  4843.4    0.05       0  4998.7    0.05       0
  5002.7    0.05       0  5011.8    0.12       0  5148.1    0.05       0
  5398.8    0.12       0  5411.3    0.05       0  5521.8    0.12       0
Bank Sta=4998.7,5002.7
Exp/Cntr=0.3,0.1

Type RM Length L Ch R = 1,4297,406,406,406
BEGIN DESCRIPTION:
LIME HOLLOW CREEK 8.0
END DESCRIPTION:
XS GIS Cut Line= 3
      2880125.56     10178846.86      2879434.72     10177477.94
      2879107.00     10177048.21
#Sta/Elev= 30
  3537.0  931.76  3597.5  931.26  3675.5  926.43  3881.8  920.23  3926.4  916.22
  4032.3  923.96  4188.4  930.19  4314.1  933.76  4426.1  931.54  4551.5  926.28
  4589.8  923.91  4696.2  921.17  4796.3  919.11  4817.8  917.71  4908.7  914.82
  4968.9  912.58  5005.8  908.78  5006.1  908.28  5009.8  908.78  5070.3  914.67
  5138.0  916.41  5165.1  913.80  5173.4  913.91  5208.7  917.81  5270.0  921.20
  5403.0  924.97  5422.6  925.63  5522.6  929.00  5548.8  931.11  5610.8  932.19
#Mann=12,-1,0
  3537.0    0.12       0  4551.5    0.05       0  4696.2    0.12       0
  4796.3    0.05       0  4817.8    0.12       0  4908.7    0.05       0
  5005.8    0.03       0  5009.8    0.05       0  5270.0    0.12       0
  5403.0    0.05       0  5422.6    0.12       0  5548.8    0.05       0
Bank Sta=5005.8,5009.8
Exp/Cntr=0.3,0.1

Type RM Length L Ch R = 1,3891,990,990,990
BEGIN DESCRIPTION:
LIME HOLLOW CREEK 7.0
END DESCRIPTION:
XS GIS Cut Line= 3
      2880193.99     10178821.79      2879690.79     10177169.78
      2879707.57     10176233.38
#Sta/Elev= 30
  3382.0  930.37  3598.7  922.12  3706.1  919.10  3738.9  917.27  3756.9  913.48
  3771.7  912.78  3788.6  919.65  3892.7  923.51  4148.7  931.38  4395.5  922.28
  4525.6  916.75  4676.9  914.81  4727.9  912.48  4791.9  915.67  4812.8  911.10
  4831.6  909.70  4959.1  909.61  4998.9  905.80  4999.2  905.30  5002.9  905.80
  5032.3  911.57  5044.3  916.95  5140.0  919.06  5305.6  927.62  5359.9  928.34
  5405.0  930.32  5658.9  936.82  5828.7  942.27  5895.7  943.22  6045.5  960.44
#Mann=12,-1,0
  3382.0    0.05       0  3598.7    0.12       0  3788.6    0.05       0
  3892.7    0.12       0  4395.5    0.05       0  4998.9    0.03       0
  5002.9    0.05       0  5140.0    0.12       0  5359.9    0.05       0
  5405.0    0.12       0  5658.9    0.05       0  5828.7    0.12       0
Bank Sta=4998.9,5002.9
Exp/Cntr=0.3,0.1

Type RM Length L Ch R = 1,2901,306,306,306
BEGIN DESCRIPTION:
LIME HOLLOW CREEK 6.0
END DESCRIPTION:
XS GIS Cut Line= 6
      2880923.85     10178885.62      2880777.60     10177855.19
      2880601.53     10177388.86      2880480.37     10177301.98
      2880214.44     10177166.88      2880183.45     10177143.76
#Sta/Elev= 30
  3403.3  929.42  3615.6  925.89  3615.9  925.39  3620.3  925.89  3849.0  927.80
  4061.8  937.86  4183.6  932.85  4425.9  932.06  4576.7  931.85  4721.5  931.29
  4726.8  929.38  4743.8  931.64  4807.1  931.21  4812.5  928.86  4830.7  931.92
  4842.0  929.39  4860.8  932.05  4979.3  932.44  4994.1  929.14  5000.2  931.44
  5008.8  929.46  5015.0  932.76  5044.4  929.91  5050.6  933.02  5065.3  933.13
  5080.1  931.16  5123.6  933.17  5344.9  932.06  5378.6  932.70  5428.6  933.62
#Mann=9,-1,0
  3403.3    0.05       0  3615.6    0.03       0  3620.3    0.05       0
  4425.9    0.12       0  4576.7    0.05       0  4743.8    0.12       0
  4830.7    0.05       0  5344.9    0.12       0  5378.6    0.05       0
Bank Sta=3615.6,3620.3
Exp/Cntr=0.3,0.1

Type RM Length L Ch R = 1,2595,554,554,554
BEGIN DESCRIPTION:
LIME HOLLOW CREEK 5.0
END DESCRIPTION:
XS GIS Cut Line= 3
      2880979.07     10177945.28      2880753.37     10177012.09
      2880682.08     10176666.46
#Sta/Elev= 30
  4197.0  926.01  4219.8  926.00  4273.6  921.31  4415.3  912.33  4477.0  911.33
  4600.5  905.90  4741.3  903.60  4908.6  904.37  4955.6  902.21  4991.4  898.09
  4997.5  893.87  5019.9  893.16  5020.3  892.66  5024.6  893.16  5032.6  893.68
  5039.3  897.59  5063.5  904.11  5094.3  909.76  5123.0  912.64  5128.2  911.57
  5176.5  915.96  5237.7  913.72  5258.2  914.45  5266.3  915.09  5278.6  918.72
  5299.0  920.11  5400.3  920.32  5467.4  924.98  5482.8  929.20  5510.0  930.90
#Mann=5,-1,0
  4197.0    0.05       0  4273.6    0.12       0  5019.9    0.07       0
  5024.6    0.12       0  5400.3    0.05       0
Bank Sta=5019.9,5024.6
Exp/Cntr=0.3,0.1

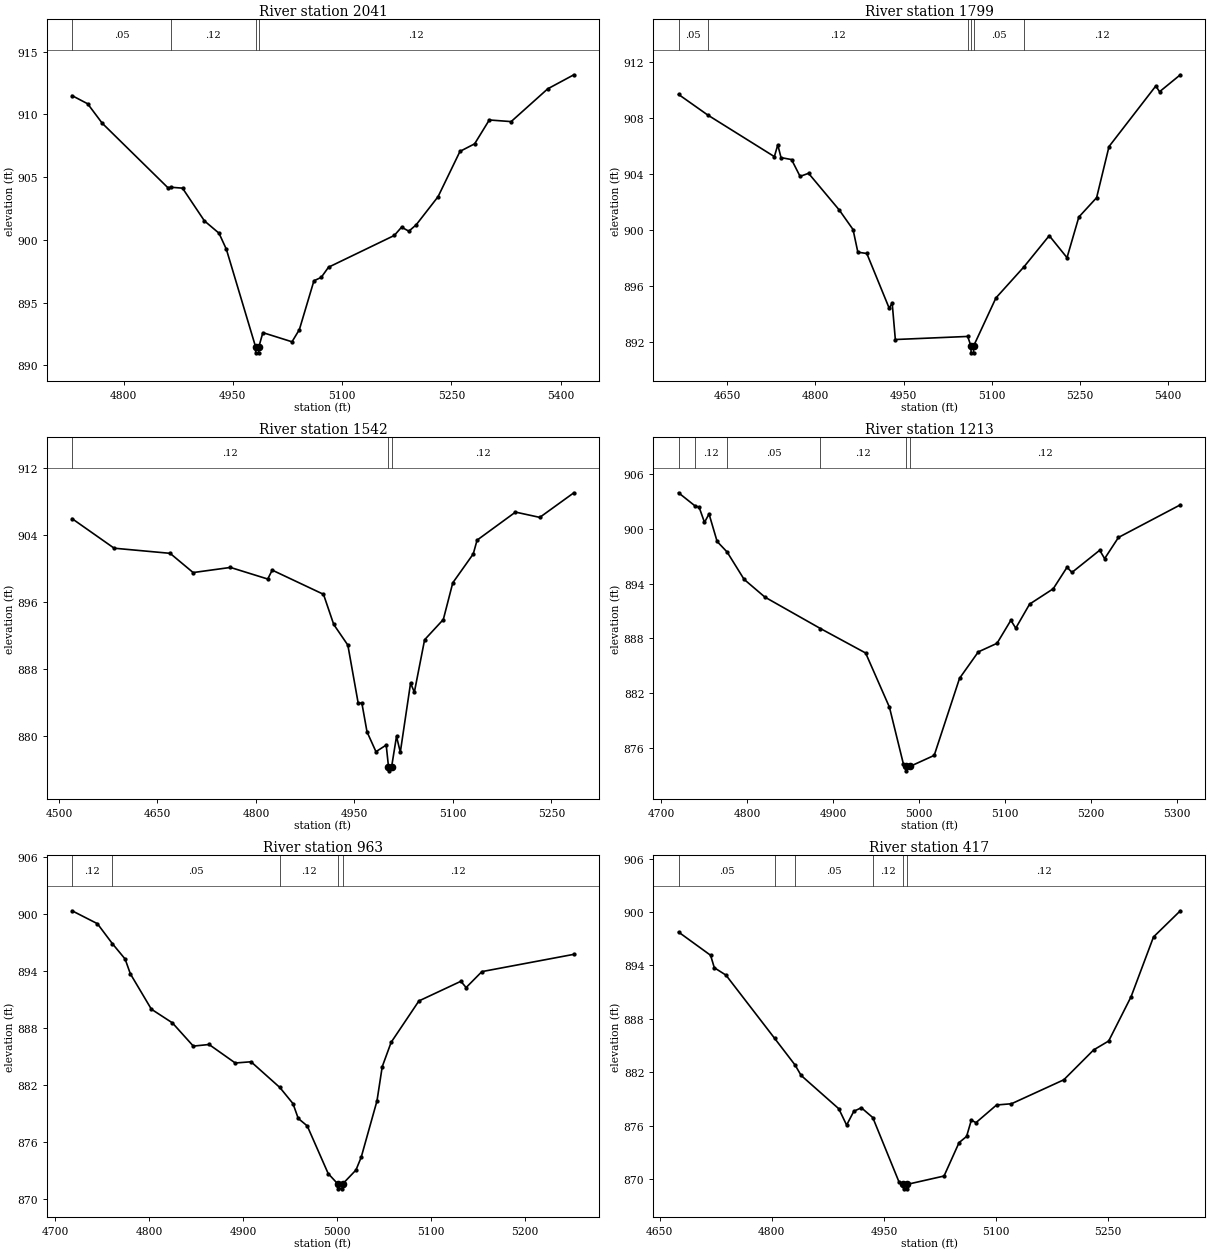
Type RM Length L Ch R = 1,2041,242,242,242
BEGIN DESCRIPTION:
LIME HOLLOW CREEK 4.0
END DESCRIPTION:
XS GIS Cut Line= 3
      2881254.67     10177654.44      2881280.71     10177246.46
      2881259.07     10176967.31
#Sta/Elev= 30
  4729.3  911.49  4750.7  910.84  4770.7  909.29  4860.9  904.15  4865.0  904.19
  4880.9  904.12  4911.0  901.51  4931.0  900.53  4941.1  899.25  4981.1  891.50
  4981.4  891.00  4985.5  891.00  4985.8  891.50  4991.2  892.61  5031.2  891.88
  5041.3  892.85  5061.3  896.74  5071.3  897.01  5081.3  897.82  5171.6  900.35
  5181.6  901.01  5191.6  900.69  5201.7  901.20  5231.7  903.44  5261.8  907.05
  5281.9  907.65  5302.0  909.55  5332.0  909.42  5382.2  912.03  5418.1  913.15
#Mann=4,-1,0
  4729.3    0.05       0  4865.0    0.12       0  4981.1    0.07       0
  4985.8    0.12       0
Bank Sta=4981.1,4985.8
Exp/Cntr=0.3,0.1

Type RM Length L Ch R = 1,1799,257,257,257
BEGIN DESCRIPTION:
Mapping XS e6de02b4
END DESCRIPTION:
XS GIS Cut Line= 3
      2881382.97     10177772.38      2881522.32     10177453.61
      2881466.97     10176951.65
#Sta/Elev= 30
  4567.6  909.67  4617.2  908.20  4730.5  905.23  4736.3  906.07  4741.8  905.16
  4759.7  905.02  4774.2  903.82  4788.6  904.04  4840.8  901.42  4864.2  900.03
  4872.4  898.41  4887.6  898.32  4925.7  894.41  4930.7  894.80  4936.1  892.18
  5059.1  892.40  5064.5  891.73  5064.9  891.23  5069.0  891.23  5069.3  891.73
  5107.1  895.15  5154.8  897.37  5197.7  899.59  5227.9  898.02  5248.0  900.92
  5278.2  902.30  5299.3  905.95  5378.8  910.27  5385.2  909.86  5420.5  911.07
#Mann=6,-1,0
  4567.6    0.05       0  4617.2    0.12       0  5059.1    0.05       0
  5064.5    0.07       0  5069.3    0.05       0  5154.8    0.12       0
Bank Sta=5064.5,5069.3
Exp/Cntr=0.3,0.1

Type RM Length L Ch R = 1,1542,329,329,329
BEGIN DESCRIPTION:
LIME HOLLOW CREEK 3.0
END DESCRIPTION:
XS GIS Cut Line= 3
      2881459.35     10177707.44      2881700.65     10177438.95
      2881906.39     10177092.18
#Sta/Elev= 30
  4519.9  905.92  4584.0  902.40  4669.2  901.79  4704.3  899.50  4761.1  900.11
  4817.9  898.73  4824.7  899.79  4902.8  896.91  4918.4  893.32  4939.9  890.86
  4955.5  884.01  4961.3  883.93  4969.1  880.53  4982.7  878.17  4998.3  878.96
  5001.8  876.39  5002.1  875.89  5006.6  876.39  5014.0  879.99  5019.8  878.11
  5035.4  886.33  5041.2  885.26  5056.8  891.50  5085.3  893.91  5099.7  898.28
  5130.9  901.72  5136.7  903.36  5195.2  906.70  5232.2  906.07  5284.1  909.00
#Mann=3,-1,0
  4519.9    0.12       0  5001.8    0.07       0  5006.6    0.12       0
Bank Sta=5001.8,5006.6
Exp/Cntr=0.3,0.1

Type RM Length L Ch R = 1,1213,250,250,250
BEGIN DESCRIPTION:
LIME HOLLOW CREEK 2.0
END DESCRIPTION:
XS GIS Cut Line= 3
      2881921.41     10177786.01      2881967.27     10177638.61
      2882173.64     10177261.91
#Sta/Elev= 30
  4720.2  903.95  4738.9  902.55  4744.2  902.36  4750.4  900.71  4755.7  901.63
  4765.1  898.62  4776.7  897.47  4796.5  894.47  4820.7  892.53  4885.3  889.09
  4937.9  886.41  4965.6  880.48  4981.8  874.28  4985.0  874.01  4985.4  873.51
  4989.9  874.01  5017.7  875.20  5047.2  883.64  5069.0  886.53  5090.8  887.47
  5106.9  889.99  5112.6  889.13  5128.7  891.76  5156.2  893.44  5172.3  895.80
  5178.0  895.23  5210.3  897.66  5216.0  896.74  5232.1  899.06  5304.1  902.63
#Mann=6,-1,0
  4720.2    0.05       0  4738.9    0.12       0  4776.7    0.05       0
  4885.3    0.12       0  4985.0    0.07       0  4989.9    0.12       0
Bank Sta=4985,4989.9
Exp/Cntr=0.3,0.1

Type RM Length L Ch R = 1,963,546,546,546
BEGIN DESCRIPTION:
Mapping XS fc85adaa
END DESCRIPTION:
XS GIS Cut Line= 2
      2882114.67     10177907.22      2882353.79     10177428.97
#Sta/Elev= 30
  4717.8  900.35  4744.8  898.99  4760.8  896.88  4774.3  895.27  4779.9  893.71
  4802.3  889.98  4824.7  888.54  4847.0  886.09  4863.8  886.26  4891.7  884.31
  4908.5  884.44  4939.2  881.73  4953.2  880.03  4958.8  878.47  4968.4  877.68
  4990.7  872.66  5001.1  871.55  5001.5  871.05  5005.6  871.05  5006.0  871.55
  5020.3  873.03  5025.9  874.38  5042.7  880.31  5048.3  883.92  5057.8  886.49
  5087.4  890.85  5132.1  892.92  5137.7  892.26  5154.5  893.94  5252.5  895.76
#Mann=5,-1,0
  4717.8    0.12       0  4760.8    0.05       0  4939.2    0.12       0
  5001.1    0.07       0  5006.0    0.12       0
Bank Sta=5001.1,5006
Exp/Cntr=0.3,0.1

Type RM Length L Ch R = 1,417,91,91,91
BEGIN DESCRIPTION:
Mapping XS b93628d6
END DESCRIPTION:
XS GIS Cut Line= 3
      2882675.18     10178236.14      2882720.99     10177842.99
      2882728.60     10177567.20
#Sta/Elev= 30
  4675.1  897.74  4718.0  895.13  4723.0  893.73  4738.6  892.90  4803.8  885.79
  4831.1  882.80  4839.2  881.63  4889.6  877.89  4900.1  876.05  4909.7  877.60
  4919.8  878.00  4935.1  876.90  4970.1  869.69  4976.0  869.39  4976.4  868.89
  4980.7  868.89  4981.0  869.39  5030.5  870.33  5050.6  874.08  5060.7  874.78
  5067.0  876.60  5073.3  876.33  5100.8  878.31  5120.8  878.45  5190.8  881.14
  5230.8  884.50  5250.9  885.50  5280.9  890.48  5310.9  897.19  5346.8  900.13
#Mann=6,-1,0
  4675.1    0.05       0  4803.8    0.12       0  4831.1    0.05       0
  4935.1    0.12       0  4976.0    0.07       0  4981.0    0.12       0
Bank Sta=4976,4981
Exp/Cntr=0.3,0.1

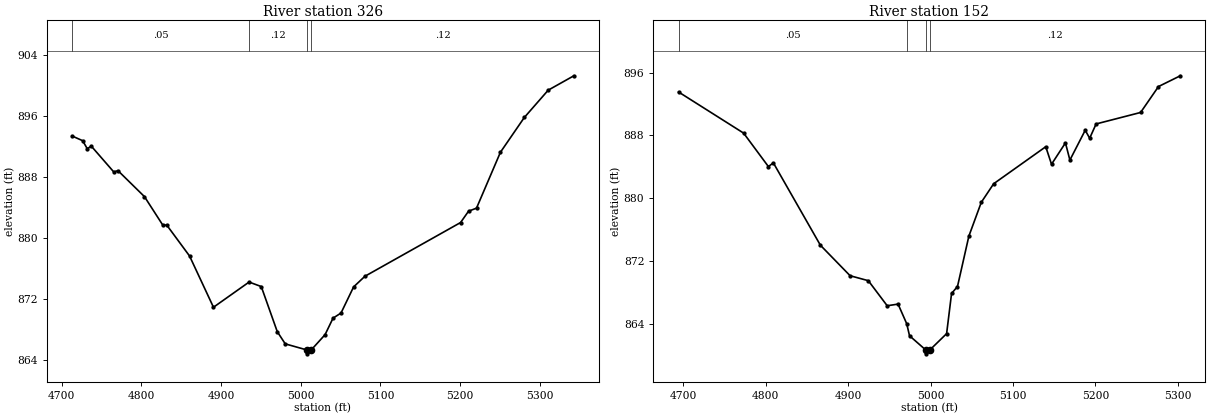
Type RM Length L Ch R = 1,326,174,174,174
BEGIN DESCRIPTION:
Mapping XS 8afc43c5
END DESCRIPTION:
XS GIS Cut Line= 3
      2882775.18     10178185.91      2882807.73     10178075.24
      2882792.54     10177560.92
#Sta/Elev= 30
  4712.9  893.42  4726.2  892.80  4731.9  891.76  4737.1  892.08  4765.3  888.69
  4770.5  888.87  4803.8  885.45  4826.8  881.71  4831.8  881.71  4860.4  877.65
  4890.4  870.92  4935.1  874.23  4950.4  873.64  4970.5  867.71  4980.5  866.11
  5008.0  865.30  5008.3  864.80  5013.0  865.30  5030.5  867.32  5040.5  869.49
  5050.5  870.16  5066.3  873.59  5080.5  874.99  5200.6  882.05  5210.6  883.54
  5220.6  883.94  5250.6  891.28  5280.6  895.85  5310.6  899.44  5342.8  901.33
#Mann=4,-1,0
  4712.9    0.05       0  4935.1    0.12       0  5008.0    0.07       0
  5013.0    0.12       0
Bank Sta=5008,5013
Exp/Cntr=0.3,0.1

Type RM Length L Ch R = 1,152,0,0,0
BEGIN DESCRIPTION:
LIME HOLLOW CREEK 1.0
END DESCRIPTION:
XS GIS Cut Line= 3
      2882797.34     10178184.63      2883018.24     10177853.88
      2882937.94     10177658.58
#Sta/Elev= 30
  4694.1  893.54  4773.1  888.30  4803.1  884.05  4809.2  884.51  4866.2  874.04
  4902.3  870.15  4924.4  869.52  4947.3  866.33  4960.5  866.54  4971.0  864.04
  4974.4  862.51  4994.0  860.71  4994.4  860.21  4999.1  860.71  5019.4  862.78
  5025.4  867.89  5032.6  868.78  5046.4  875.19  5061.5  879.50  5076.5  881.86
  5139.7  886.57  5146.7  884.34  5163.6  887.06  5169.0  884.87  5187.6  888.67
  5193.0  887.65  5200.8  889.47  5254.8  890.93  5276.5  894.23  5303.0  895.60
#Mann=4,-1,0
  4694.1    0.05       0  4971.0    0.12       0  4994.0    0.07       0
  4999.1    0.12       0
Bank Sta=4994,4999.1
Exp/Cntr=0.3,0.1

Chan Stop Cuts=-1