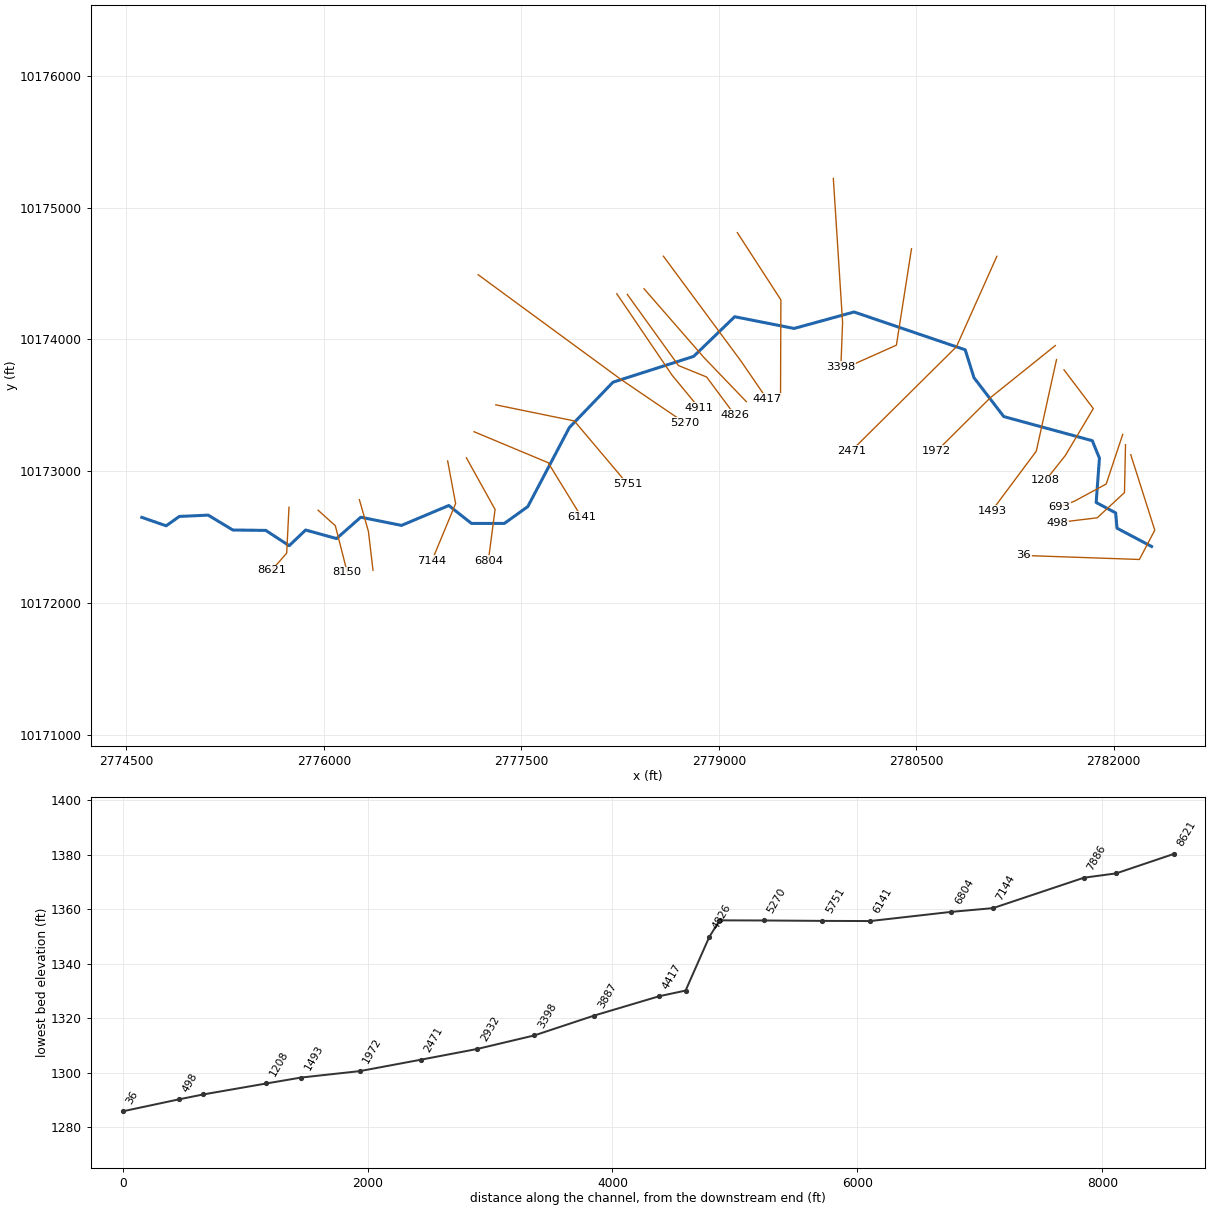
--- SANDY 17.prj (project) ---

Proj Title=SANDY 17 Base Level Engineering
Current Plan=p01
Default Exp/Contr=0.3,0.1
English Units
Geom File=g01
Flow File=f01
Plan File=p01
BEGIN DESCRIPTION:
SANDY 17
END DESCRIPTION:

--- SANDY 17.p01 (plan) ---

Plan Title=Multiple Run
Short Identifier=Multiple
Geom File=g01
Flow File=f01
Subcritical Flow
K Sum by GR= 0
Std Step Tol= 0.01
Critical Tol= 0.01
Num of Std Step Trials= 20
Max Error Tol= 0.3
Flow Tol Ratio= 0.001
Split Flow NTrial= 30
Split Flow Tol= 0.02
Split Flow Ratio= 0.02
Log Output Level= 0
Friction Slope Method= 1
Unsteady Friction Slope Method= 2
Unsteady Bridges Friction Slope Method= 1
Parabolic Critical Depth
Global Vel Dist=  1 , 1 , 1
Global Log Level= 0
CheckData=True
Encroach Param= -1, 0, 0, 0
BEGIN DESCRIPTION:
Multiple Run
END DESCRIPTION:

--- SANDY 17.f01 (steady flow) ---

Flow Title=Multiple
Number of Profiles=7
Profile Names=10-year,25-year,50-year,1pct_min,100-year,1pct_plu,500-year
River Rch & RM= SANDY 17,Reach-1,8621
     400     639    1304    1107    1815    2976    2609
River Rch & RM= SANDY 17,Reach-1,5270
     579     956    1794    1371    2515    4614    3606
Boundary for River Rch & Prof#=SANDY 17,Reach-1,1
Up Type=0
Dn Type=3
Dn Slope=0.005
Boundary for River Rch & Prof#=SANDY 17,Reach-1,2
Up Type=0
Dn Type=3
Dn Slope=0.005
Boundary for River Rch & Prof#=SANDY 17,Reach-1,3
Up Type=0
Dn Type=3
Dn Slope=0.005
Boundary for River Rch & Prof#=SANDY 17,Reach-1,4
Up Type=0
Dn Type=3
Dn Slope=0.005
Boundary for River Rch & Prof#=SANDY 17,Reach-1,5
Up Type=0
Dn Type=3
Dn Slope=0.005
Boundary for River Rch & Prof#=SANDY 17,Reach-1,6
Up Type=0
Dn Type=3
Dn Slope=0.005
Boundary for River Rch & Prof#=SANDY 17,Reach-1,7
Up Type=0
Dn Type=3
Dn Slope=0.005

--- SANDY 17.g01 (geometry) ---

Geom Title=Existing Conditions

River Reach=SANDY 17,Reach-1
Reach XY= 30
      2774616.75     10172649.00      2774801.75     10172585.00
      2774902.00     10172656.00      2775120.75     10172666.00
      2775308.25     10172553.00      2775558.25     10172550.00
      2775736.25     10172434.00      2775861.25     10172553.00
      2776095.75     10172488.00      2776280.00     10172650.00
      2776589.50     10172588.00      2776948.50     10172739.00
      2777120.75     10172603.00      2777370.75     10172603.00
      2777548.75     10172731.00      2777864.50     10173331.00
      2778195.75     10173675.00      2778808.50     10173871.00
      2779120.25     10174172.00      2779571.50     10174083.00
      2780027.00     10174208.00      2780871.25     10173921.00
      2780938.00     10173709.00      2781164.25     10173414.00
      2781836.75     10173231.00      2781891.00     10173098.00
      2781866.00     10172762.00      2782014.25     10172683.00
      2782024.25     10172567.00      2782287.00     10172428.00

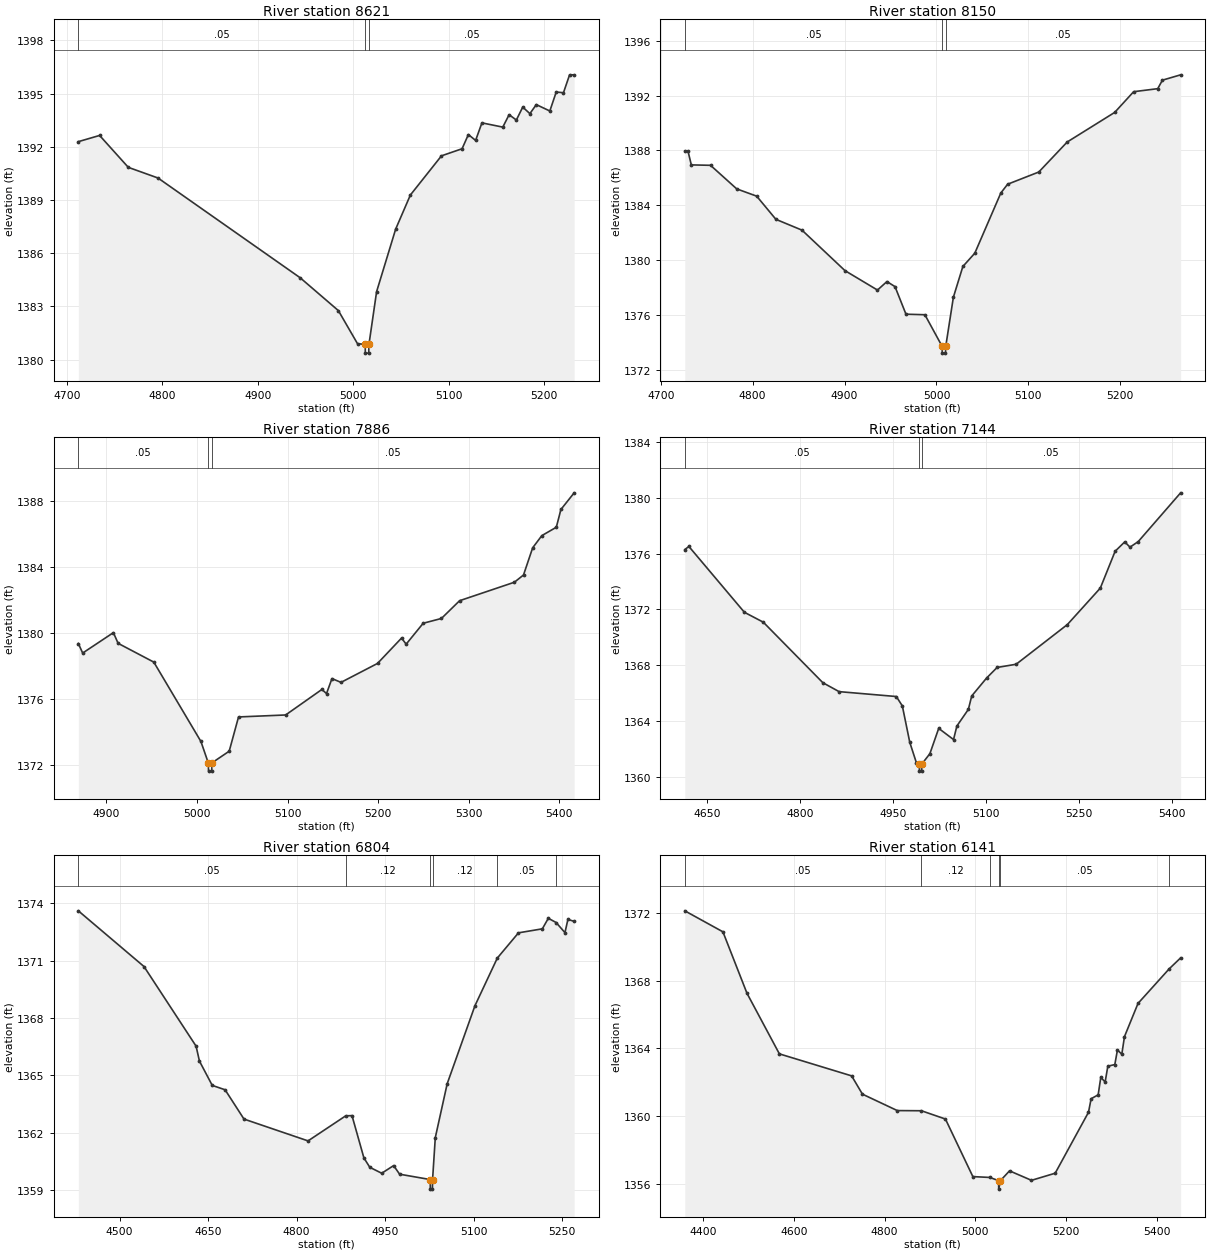
Type RM Length L Ch R = 1,8621,471,471,471
BEGIN DESCRIPTION:
SANDY 17 16.0
END DESCRIPTION:
XS GIS Cut Line= 3
      2775734.68     10172725.40      2775717.21     10172377.42
      2775604.35     10172248.44
#Sta/Elev= 30
  4711.8 1392.29  4734.1 1392.64  4764.2 1390.84  4795.3 1390.24  4944.4 1384.61
  4984.4 1382.76  5004.5 1380.89  5012.5 1380.86  5012.7 1380.36  5016.2 1380.36
  5016.5 1380.86  5024.5 1383.83  5044.5 1387.36  5059.9 1389.28  5092.5 1391.49
  5114.1 1391.89  5120.7 1392.69  5128.3 1392.36  5134.9 1393.35  5156.8 1393.11
  5163.4 1393.81  5171.0 1393.51  5177.7 1394.24  5185.2 1393.87  5191.9 1394.38
  5206.1 1394.02  5212.8 1395.09  5220.4 1395.05  5226.8 1396.06  5231.6 1396.06
#Mann=3,-1,0
  4711.8    0.05       0  5012.5    0.05       0  5016.5    0.05       0
Bank Sta=5012.5,5016.5
Exp/Cntr=0.3,0.1

Type RM Length L Ch R = 1,8150,264,264,264
BEGIN DESCRIPTION:
SANDY 17 15.0
END DESCRIPTION:
XS GIS Cut Line= 3
      2775955.67     10172703.13      2776086.73     10172585.70
      2776176.77     10172233.60
#Sta/Elev= 30
  4726.2 1387.96  4729.6 1387.96  4733.3 1386.94  4754.2 1386.91  4782.7 1385.19
  4804.4 1384.66  4825.3 1382.97  4853.7 1382.18  4900.4 1379.23  4935.8 1377.81
  4946.1 1378.43  4954.9 1378.06  4966.8 1376.05  4987.4 1376.01  5006.1 1373.71
  5006.3 1373.21  5009.8 1373.21  5010.1 1373.71  5018.4 1377.29  5028.7 1379.53
  5041.7 1380.50  5070.0 1384.89  5077.4 1385.53  5111.3 1386.42  5142.2 1388.61
  5193.9 1390.77  5214.5 1392.28  5240.7 1392.50  5245.8 1393.12  5265.6 1393.51
#Mann=3,-1,0
  4726.2    0.05       0  5006.1    0.05       0  5010.1    0.05       0
Bank Sta=5006.1,5010.1
Exp/Cntr=0.3,0.1

Type RM Length L Ch R = 1,7886,742,742,742
BEGIN DESCRIPTION:
SANDY 17 14.0
END DESCRIPTION:
XS GIS Cut Line= 3
      2776269.48     10172783.19      2776338.00     10172542.70
      2776372.88     10172247.62
#Sta/Elev= 30
  4869.1 1379.36  4873.9 1378.78  4907.8 1380.02  4913.0 1379.37  4952.4 1378.23
  5004.4 1373.41  5012.5 1372.11  5012.8 1371.61  5016.3 1371.61  5016.5 1372.11
  5035.6 1372.82  5045.9 1374.90  5097.9 1375.02  5137.9 1376.57  5143.0 1376.32
  5149.0 1377.23  5159.0 1377.00  5199.3 1378.15  5225.8 1379.69  5230.9 1379.32
  5249.7 1380.59  5269.8 1380.88  5289.9 1381.96  5350.3 1383.08  5360.4 1383.52
  5370.5 1385.17  5380.6 1385.91  5396.6 1386.42  5401.7 1387.50  5416.3 1388.51
#Mann=3,-1,0
  4869.1    0.05       0  5012.5    0.05       0  5016.5    0.05       0
Bank Sta=5012.5,5016.5
Exp/Cntr=0.3,0.1

Type RM Length L Ch R = 1,7144,340,340,340
BEGIN DESCRIPTION:
SANDY 17 13.0
END DESCRIPTION:
XS GIS Cut Line= 3
      2776939.99     10173077.45      2777000.45     10172753.66
      2776820.53     10172319.98
#Sta/Elev= 30
  4614.4 1376.29  4621.0 1376.51  4710.4 1371.80  4740.9 1371.09  4836.8 1366.76
  4863.0 1366.12  4955.2 1365.77  4964.9 1365.10  4976.9 1362.49  4987.7 1361.01
  4992.2 1360.93  4992.5 1360.43  4996.0 1360.43  4996.2 1360.93  5009.3 1361.68
  5023.5 1363.49  5047.4 1362.69  5052.8 1363.66  5071.3 1364.85  5076.7 1365.81
  5100.6 1367.09  5117.6 1367.85  5148.3 1368.08  5230.8 1370.92  5283.9 1373.53
  5307.8 1376.17  5323.3 1376.84  5331.7 1376.46  5345.0 1376.86  5413.3 1380.35
#Mann=3,-1,0
  4614.4    0.05       0  4992.2    0.05       0  4996.2    0.05       0
Bank Sta=4992.2,4996.2
Exp/Cntr=0.3,0.1

Type RM Length L Ch R = 1,6804,663,663,663
BEGIN DESCRIPTION:
SANDY 17 12.0
END DESCRIPTION:
XS GIS Cut Line= 3
      2777082.41     10173100.35      2777300.10     10172709.32
      2777249.04     10172319.69
#Sta/Elev= 30
  4430.1 1373.60  4541.4 1370.69  4629.7 1366.53  4635.4 1365.75  4657.1 1364.48
  4678.9 1364.25  4710.9 1362.72  4819.5 1361.58  4883.4 1362.89  4894.0 1362.90
  4914.2 1360.69  4924.2 1360.20  4944.4 1359.89  4964.6 1360.29  4974.7 1359.84
  5026.6 1359.56  5026.8 1359.06  5030.3 1359.06  5030.6 1359.56  5035.2 1361.75
  5055.4 1364.57  5102.4 1368.64  5140.3 1371.13  5176.2 1372.45  5216.7 1372.66
  5226.8 1373.21  5240.0 1372.99  5255.0 1372.46  5260.0 1373.15  5270.6 1373.05
#Mann=6,-1,0
  4430.1    0.05       0  4883.4    0.12       0  5026.6    0.07       0
  5030.6    0.12       0  5140.3    0.05       0  5240.0    0.12       0
Bank Sta=5026.6,5030.6
Exp/Cntr=0.3,0.1

Type RM Length L Ch R = 1,6141,390,390,390
BEGIN DESCRIPTION:
SANDY 17 11.0
END DESCRIPTION:
XS GIS Cut Line= 3
      2777140.19     10173299.21      2777703.21     10173064.06
      2777955.71     10172653.08
#Sta/Elev= 30
  4359.7 1372.12  4443.7 1370.88  4496.7 1367.25  4568.1 1363.67  4727.3 1362.37
  4751.1 1361.29  4827.9 1360.32  4881.1 1360.31  4934.0 1359.82  4994.4 1356.42
  5031.9 1356.37  5051.1 1356.18  5051.4 1355.68  5055.1 1356.18  5075.2 1356.76
  5123.6 1356.20  5175.8 1356.62  5249.2 1360.22  5255.0 1361.02  5270.5 1361.25
  5276.3 1362.28  5285.9 1362.01  5291.8 1362.94  5307.2 1363.04  5313.0 1363.90
  5322.6 1363.65  5328.5 1364.69  5358.3 1366.65  5426.9 1368.69  5452.2 1369.34
#Mann=6,-1,0
  4359.7    0.05       0  4881.1    0.12       0  5031.9    0.05       0
  5051.1    0.07       0  5055.1    0.05       0  5426.9    0.12       0
Bank Sta=5051.1,5055.1
Exp/Cntr=0.3,0.1

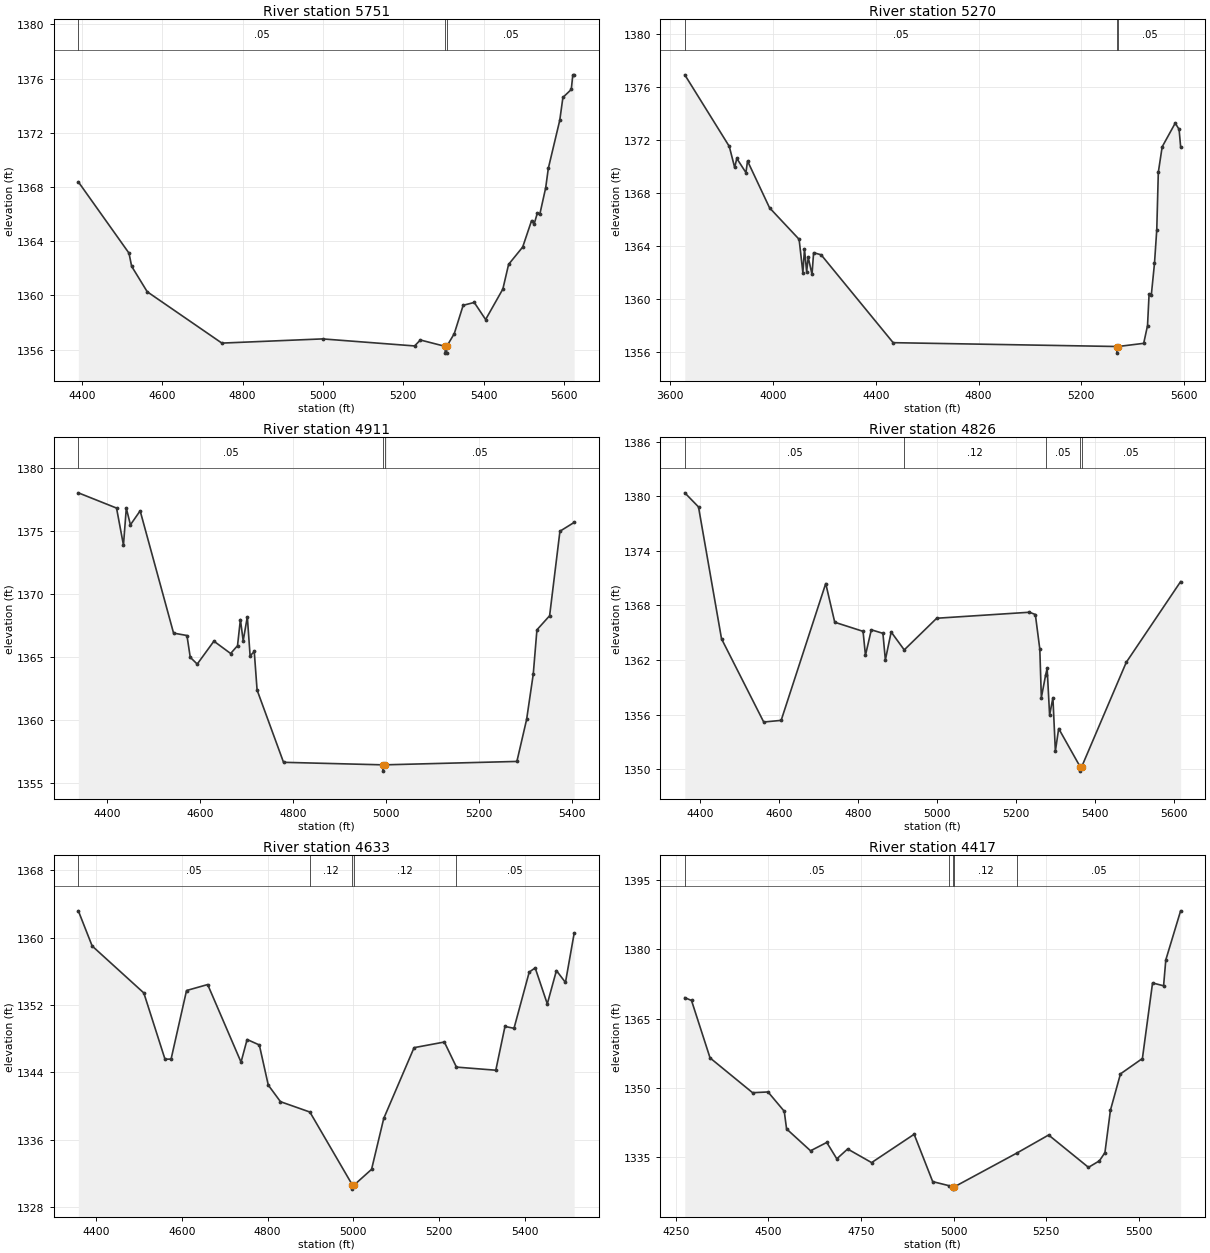
Type RM Length L Ch R = 1,5751,481,481,481
BEGIN DESCRIPTION:
SANDY 17 10.0
END DESCRIPTION:
XS GIS Cut Line= 3
      2777305.67     10173503.11      2777902.00     10173381.00
      2778305.70     10172903.09
#Sta/Elev= 30
  4391.3 1368.38  4517.4 1363.12  4524.0 1362.15  4562.8 1360.27  4748.6 1356.48
  4999.3 1356.79  5228.4 1356.27  5242.7 1356.71  5304.4 1356.24  5304.6 1355.74
  5308.1 1355.74  5308.4 1356.24  5327.2 1357.18  5349.3 1359.27  5376.9 1359.48
  5405.2 1358.22  5448.1 1360.47  5462.4 1362.29  5497.5 1363.57  5519.6 1365.52
  5526.1 1365.28  5533.9 1366.07  5540.4 1366.03  5554.7 1367.94  5561.3 1369.38
  5589.8 1372.93  5597.6 1374.61  5618.4 1375.20  5622.3 1376.28  5625.6 1376.28
#Mann=3,-1,0
  4391.3    0.05       0  5304.4    0.03       0  5308.4    0.05       0
Bank Sta=5304.4,5308.4
Exp/Cntr=0.3,0.1

Type RM Length L Ch R = 1,5270,359,359,359
BEGIN DESCRIPTION:
SANDY 17 9.0
END DESCRIPTION:
XS GIS Cut Line= 3
      2777171.61     10174490.84      2778255.00     10173697.00
      2778739.91     10173367.61
#Sta/Elev= 30
  3656.9 1376.92  3830.0 1371.51  3850.9 1369.92  3859.3 1370.60  3894.8 1369.53
  3901.0 1370.41  3986.7 1366.87  4101.7 1364.49  4116.4 1361.97  4122.6 1363.76
  4131.0 1362.05  4137.2 1363.13  4151.9 1361.84  4158.1 1363.48  4187.4 1363.32
  4467.6 1356.68  5338.6 1356.39  5338.9 1355.89  5343.0 1356.39  5442.5 1356.63
  5457.4 1357.97  5463.5 1360.35  5472.3 1360.31  5484.5 1362.67  5493.4 1365.23
  5499.4 1369.55  5514.4 1371.48  5565.2 1373.27  5580.2 1372.80  5586.2 1371.50
#Mann=3,-1,0
  3656.9    0.05       0  5338.6    0.03       0  5343.0    0.05       0
Bank Sta=5338.6,5343
Exp/Cntr=0.3,0.1

Type RM Length L Ch R = 1,4911,85,85,85
BEGIN DESCRIPTION:
Mapping XS 69b1591b
END DESCRIPTION:
XS GIS Cut Line= 3
      2778224.77     10174346.44      2778643.16     10173730.15
      2778848.04     10173481.86
#Sta/Elev= 30
  4337.9 1378.04  4420.1 1376.83  4435.0 1373.89  4441.1 1376.82  4450.0 1375.50
  4470.9 1376.61  4542.8 1366.90  4571.6 1366.71  4578.7 1364.98  4593.7 1364.44
  4629.6 1366.26  4665.6 1365.28  4680.4 1365.90  4686.6 1367.98  4692.6 1366.29
  4701.5 1368.20  4707.5 1365.09  4716.4 1365.44  4722.5 1362.38  4779.4 1356.64
  4992.8 1356.44  4993.1 1355.94  4997.2 1356.44  5281.5 1356.71  5302.4 1360.04
  5316.7 1363.64  5324.6 1367.16  5351.9 1368.28  5374.1 1374.99  5404.7 1375.69
#Mann=3,-1,0
  4337.9    0.05       0  4992.8    0.03       0  4997.2    0.05       0
Bank Sta=4992.8,4997.2
Exp/Cntr=0.3,0.1

Type RM Length L Ch R = 1,4826,193,193,193
BEGIN DESCRIPTION:
SANDY 17 8.0
END DESCRIPTION:
XS GIS Cut Line= 4
      2778304.62     10174341.25      2778693.51     10173801.33
      2778907.05     10173714.52      2779121.48     10173425.73
#Sta/Elev= 30
  4361.7 1380.38  4396.4 1378.83  4454.7 1364.33  4561.5 1355.18  4605.7 1355.36
  4718.6 1370.41  4741.4 1366.15  4813.1 1365.15  4819.2 1362.52  4834.0 1365.32
  4863.4 1364.93  4869.6 1362.01  4884.3 1365.08  4917.4 1363.11  4999.6 1366.59
  5234.5 1367.25  5249.4 1367.00  5260.7 1363.20  5264.6 1357.86  5275.5 1360.36
  5279.3 1361.07  5285.5 1355.94  5293.9 1357.86  5300.1 1351.98  5308.5 1354.46
  5362.6 1350.28  5362.9 1349.78  5367.0 1350.28  5479.6 1361.74  5617.3 1370.62
#Mann=5,-1,0
  4361.7    0.05       0  4917.4    0.12       0  5275.5    0.05       0
  5362.6    0.07       0  5367.0    0.05       0
Bank Sta=5362.6,5367
Exp/Cntr=0.3,0.1

Type RM Length L Ch R = 1,4633,216,216,216
BEGIN DESCRIPTION:
SANDY 17 7.0
END DESCRIPTION:
XS GIS Cut Line= 3
      2778431.35     10174384.67      2778887.97     10173861.00
      2779208.62     10173527.55
#Sta/Elev= 30
  4358.0 1363.19  4390.3 1359.01  4510.9 1353.43  4560.3 1345.56  4574.5 1345.57
  4610.6 1353.72  4659.9 1354.43  4737.8 1345.21  4752.0 1347.90  4780.5 1347.25
  4801.4 1342.48  4829.9 1340.51  4898.5 1339.28  4997.6 1330.62  4997.9 1330.12
  5002.0 1330.62  5042.5 1332.47  5070.9 1338.52  5141.7 1346.93  5212.4 1347.60
  5240.6 1344.62  5332.5 1344.25  5353.9 1349.45  5375.0 1349.23  5410.5 1355.91
  5424.4 1356.41  5452.7 1352.13  5474.0 1356.09  5495.1 1354.68  5515.4 1360.52
#Mann=5,-1,0
  4358.0    0.05       0  4898.5    0.12       0  4997.6    0.07       0
  5002.0    0.12       0  5240.6    0.05       0
Bank Sta=4997.6,5002
Exp/Cntr=0.3,0.1

Type RM Length L Ch R = 1,4417,530,530,530
BEGIN DESCRIPTION:
Mapping XS 7d0bad85
END DESCRIPTION:
XS GIS Cut Line= 3
      2778578.90     10174631.22      2779167.46     10173836.05
      2779365.26     10173548.02
#Sta/Elev= 30
  4274.2 1369.54  4292.3 1368.93  4342.4 1356.48  4457.2 1348.94  4498.9 1349.10
  4542.7 1344.92  4549.0 1341.09  4613.7 1336.35  4657.5 1338.16  4684.6 1334.61
  4713.9 1336.74  4778.6 1333.79  4893.4 1339.93  4943.5 1329.67  4988.3 1328.77
  4997.6 1328.54  4997.9 1328.04  5002.0 1328.54  5170.3 1335.84  5256.5 1339.77
  5364.1 1332.76  5393.6 1334.17  5408.5 1335.95  5423.4 1345.15  5450.5 1353.02
  5509.7 1356.35  5537.1 1372.73  5566.9 1372.11  5572.9 1377.73  5612.9 1388.36
#Mann=5,-1,0
  4274.2    0.05       0  4988.3    0.12       0  4997.6    0.07       0
  5002.0    0.12       0  5170.3    0.05       0
Bank Sta=4997.6,5002
Exp/Cntr=0.3,0.1

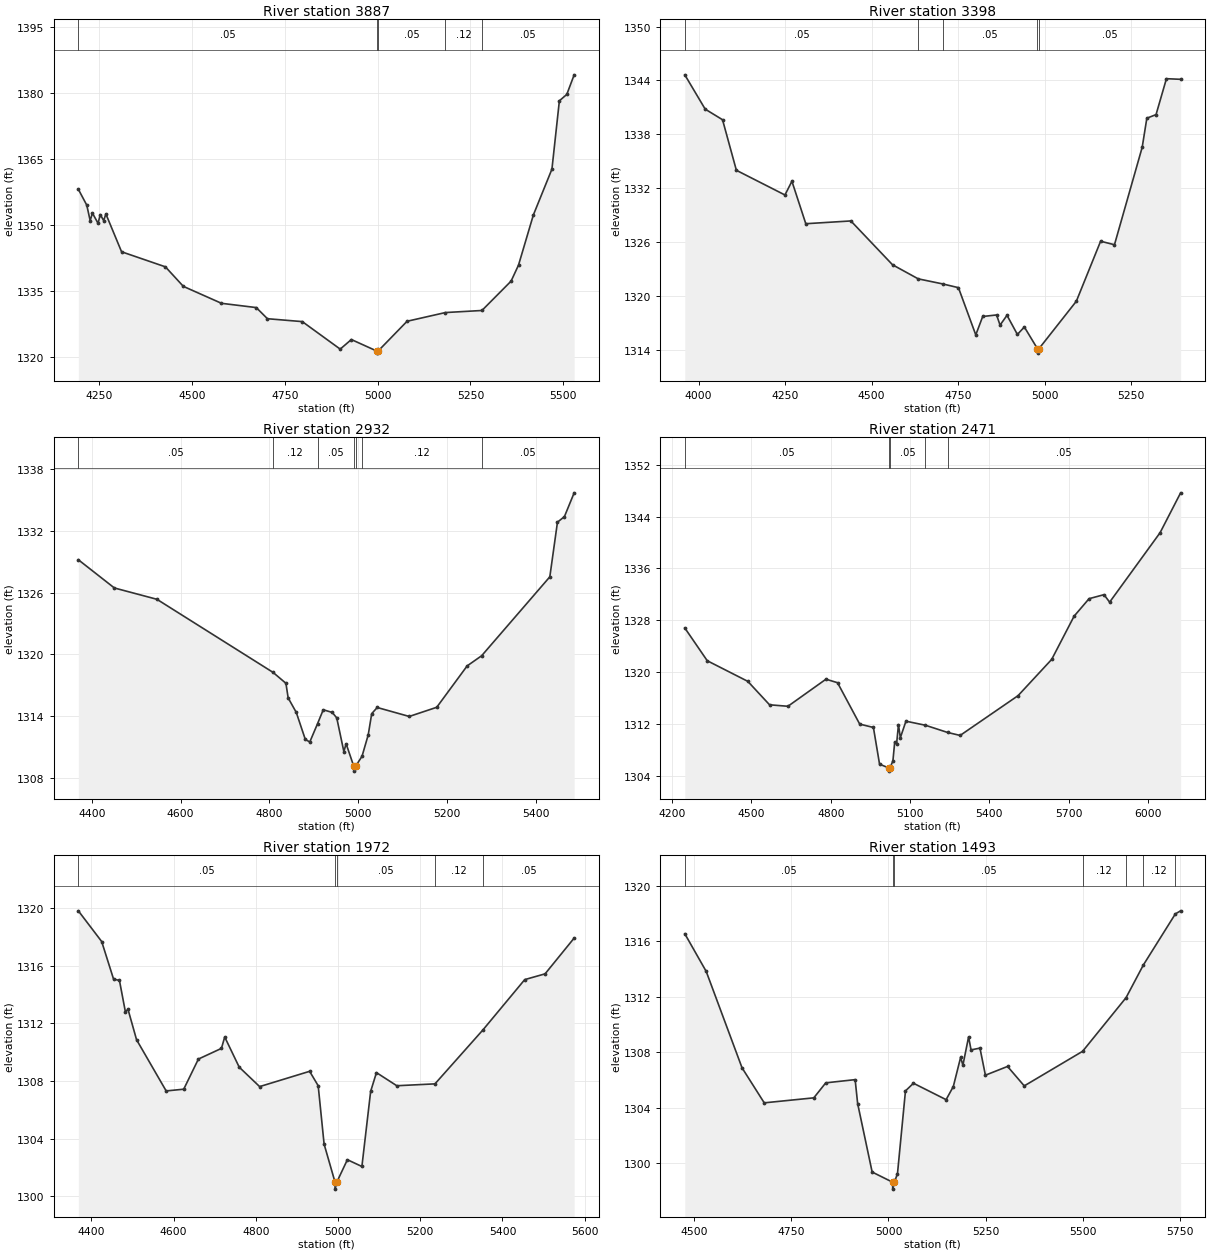
Type RM Length L Ch R = 1,3887,489,489,489
BEGIN DESCRIPTION:
SANDY 17 6.0
END DESCRIPTION:
XS GIS Cut Line= 3
      2779140.37     10174810.37      2779471.11     10174299.94
      2779468.51     10173573.36
#Sta/Elev= 30
  4194.3 1358.18  4217.0 1354.57  4226.2 1351.04  4232.2 1352.77  4247.4 1350.44
  4253.3 1352.42  4262.5 1351.07  4268.5 1352.56  4310.7 1343.97  4428.7 1340.55
  4477.0 1336.11  4579.7 1332.26  4673.3 1331.29  4703.4 1328.76  4797.3 1328.10
  4899.3 1321.85  4929.3 1324.03  4997.1 1321.44  4997.4 1320.94  5001.6 1321.44
  5079.3 1328.18  5182.5 1330.16  5280.8 1330.63  5359.3 1337.30  5379.3 1340.94
  5419.3 1352.34  5469.3 1362.76  5489.3 1378.28  5509.3 1379.73  5529.1 1384.18
#Mann=5,-1,0
  4194.3    0.05       0  4997.1    0.05       0  5001.6    0.05       0
  5182.5    0.12       0  5280.8    0.05       0
Bank Sta=4997.1,5001.6
Exp/Cntr=0.3,0.1

Type RM Length L Ch R = 1,3398,466,466,466
BEGIN DESCRIPTION:
SANDY 17 5.0
END DESCRIPTION:
XS GIS Cut Line= 3
      2779869.54     10175221.85      2779939.86     10174128.06
      2779926.84     10173792.16
#Sta/Elev= 30
  3960.3 1344.63  4019.2 1340.81  4069.3 1339.63  4109.3 1334.00  4249.6 1331.25
  4269.7 1332.78  4309.8 1328.05  4440.0 1328.36  4560.3 1323.48  4634.6 1321.91
  4704.8 1321.35  4750.7 1320.93  4800.8 1315.67  4820.8 1317.72  4860.9 1317.89
  4870.9 1316.76  4891.0 1317.85  4921.0 1315.72  4941.1 1316.55  4978.8 1314.14
  4979.2 1313.64  4983.4 1314.14  5091.3 1319.42  5161.4 1326.10  5201.4 1325.71
  5281.5 1336.56  5294.9 1339.80  5321.5 1340.20  5351.5 1344.20  5392.5 1344.13
#Mann=5,-1,0
  3960.3    0.05       0  4634.6    0.12       0  4704.8    0.05       0
  4978.8    0.05       0  4983.4    0.05       0
Bank Sta=4978.8,4983.4
Exp/Cntr=0.3,0.1

Type RM Length L Ch R = 1,2932,461,461,461
BEGIN DESCRIPTION:
SANDY 17 4.0
END DESCRIPTION:
XS GIS Cut Line= 3
      2780463.29     10174687.91      2780348.71     10173956.19
      2780005.66     10173803.10
#Sta/Elev= 30
  4369.9 1329.19  4451.0 1326.45  4546.8 1325.35  4808.3 1318.25  4837.3 1317.19
  4842.3 1315.77  4860.6 1314.36  4880.9 1311.74  4891.0 1311.49  4908.5 1313.27
  4921.3 1314.62  4941.6 1314.36  4951.7 1313.83  4967.7 1310.56  4972.8 1311.32
  4989.8 1309.16  4990.2 1308.66  4994.5 1309.16  5008.6 1310.10  5022.6 1312.19
  5030.4 1314.24  5042.8 1314.84  5114.9 1313.97  5176.8 1314.86  5245.3 1318.88
  5278.0 1319.87  5431.4 1327.53  5448.6 1332.84  5464.3 1333.38  5486.2 1335.69
#Mann=7,-1,0
  4369.9    0.05       0  4808.3    0.12       0  4908.5    0.05       0
  4989.8    0.05       0  4994.5    0.05       0  5008.6    0.12       0
  5278.0    0.05       0
Bank Sta=4989.8,4994.5
Exp/Cntr=0.3,0.1

Type RM Length L Ch R = 1,2471,499,499,499
BEGIN DESCRIPTION:
SANDY 17 3.0
END DESCRIPTION:
XS GIS Cut Line= 3
      2781111.75     10174630.70      2780804.50     10173944.00
      2780005.69     10173153.11
#Sta/Elev= 30
  4247.7 1326.81  4332.7 1321.75  4486.1 1318.57  4568.4 1314.95  4638.0 1314.72
  4781.9 1318.90  4825.7 1318.36  4909.6 1311.97  4961.5 1311.45  4984.7 1305.79
  5018.7 1305.21  5019.0 1304.71  5023.4 1305.21  5035.2 1306.25  5042.2 1309.24
  5049.3 1308.93  5056.3 1311.89  5063.4 1309.86  5084.6 1312.42  5158.5 1311.79
  5242.2 1310.68  5289.7 1310.22  5508.9 1316.36  5636.2 1321.96  5721.0 1328.63
  5777.6 1331.33  5834.2 1331.95  5855.4 1330.79  6046.3 1341.51  6124.1 1347.67
#Mann=5,-1,0
  4247.7    0.05       0  5018.7    0.05       0  5023.4    0.05       0
  5158.5    0.12       0  5242.2    0.05       0
Bank Sta=5018.7,5023.4
Exp/Cntr=0.3,0.1

Type RM Length L Ch R = 1,1972,479,479,479
BEGIN DESCRIPTION:
SANDY 17 2.0
END DESCRIPTION:
XS GIS Cut Line= 3
      2781555.65     10173953.08      2781063.00     10173558.00
      2780655.70     10173153.12
#Sta/Elev= 30
  4368.5 1319.81  4425.3 1317.68  4454.1 1315.08  4468.5 1314.98  4482.9 1312.81
  4489.3 1312.98  4510.1 1310.87  4582.1 1307.32  4624.8 1307.44  4660.5 1309.53
  4716.5 1310.27  4724.5 1311.06  4759.7 1308.97  4809.4 1307.62  4931.0 1308.68
  4951.8 1307.68  4966.2 1303.63  4992.6 1301.01  4992.9 1300.51  4997.3 1301.01
  5022.8 1302.55  5058.1 1302.08  5079.4 1307.29  5093.5 1308.59  5143.0 1307.68
  5235.8 1307.81  5352.1 1311.54  5454.1 1315.04  5503.6 1315.44  5574.3 1317.92
#Mann=5,-1,0
  4368.5    0.05       0  4992.6    0.03       0  4997.3    0.05       0
  5235.8    0.12       0  5352.1    0.05       0
Bank Sta=4992.6,4997.3
Exp/Cntr=0.3,0.1

Type RM Length L Ch R = 1,1493,285,285,285
BEGIN DESCRIPTION:
Mapping XS fa762eab
END DESCRIPTION:
XS GIS Cut Line= 3
      2781564.85     10173846.78      2781411.21     10173151.50
      2781075.30     10172701.01
#Sta/Elev= 30
  4476.7 1316.53  4531.7 1313.82  4623.8 1306.88  4680.8 1304.36  4808.2 1304.72
  4838.9 1305.80  4914.4 1306.03  4920.8 1304.31  4958.1 1299.38  5010.6 1298.65
  5011.0 1298.15  5015.4 1298.65  5023.2 1299.27  5043.7 1305.22  5064.2 1305.77
  5148.1 1304.59  5166.6 1305.53  5185.4 1307.63  5191.3 1307.07  5205.9 1309.11
  5212.2 1308.17  5235.1 1308.30  5249.1 1306.35  5306.0 1306.98  5348.9 1305.58
  5498.9 1308.07  5610.5 1311.93  5654.9 1314.28  5737.2 1317.96  5750.7 1318.18
#Mann=7,-1,0
  4476.7    0.05       0  5010.6    0.03       0  5015.4    0.05       0
  5498.9    0.12       0  5610.5    0.05       0  5654.9    0.12       0
  5737.2    0.05       0
Bank Sta=5010.6,5015.4
Exp/Cntr=0.3,0.1

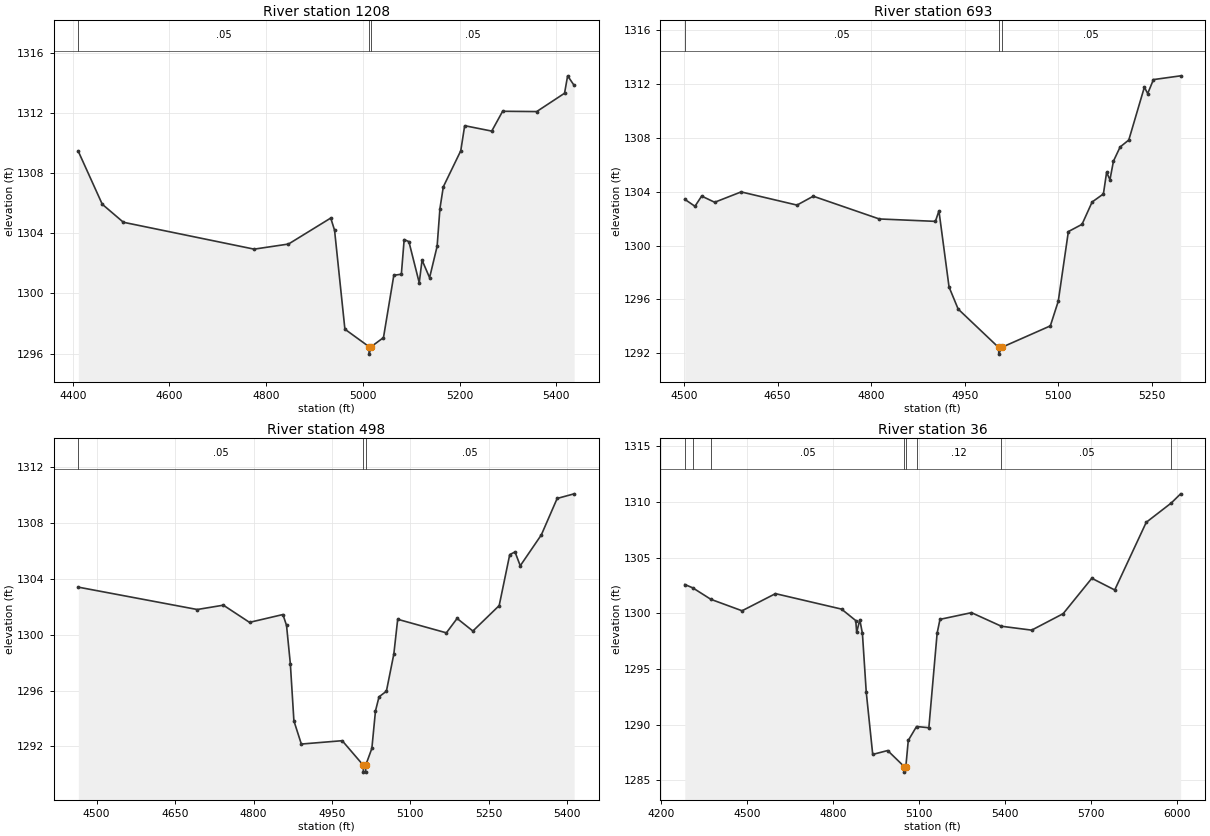
Type RM Length L Ch R = 1,1208,515,515,515
BEGIN DESCRIPTION:
Mapping XS f895f055
END DESCRIPTION:
XS GIS Cut Line= 4
      2781621.76     10173768.87      2781844.40     10173474.62
      2781632.16     10173119.15      2781481.13     10172929.05
#Sta/Elev= 30
  4411.4 1309.46  4460.9 1305.94  4504.6 1304.74  4775.1 1302.95  4846.2 1303.29
  4933.6 1305.02  4941.5 1304.21  4962.9 1297.62  5012.6 1296.46  5013.0 1295.96
  5017.5 1296.46  5042.7 1297.06  5064.1 1301.21  5079.7 1301.28  5085.5 1303.59
  5095.3 1303.45  5116.7 1300.71  5122.5 1302.22  5138.1 1301.05  5153.7 1303.14
  5159.5 1305.65  5166.5 1307.10  5202.6 1309.50  5210.7 1311.17  5266.7 1310.81
  5289.2 1312.13  5359.7 1312.11  5417.3 1313.33  5423.7 1314.49  5437.2 1313.85
#Mann=3,-1,0
  4411.4    0.05       0  5012.6    0.03       0  5017.5    0.05       0
Bank Sta=5012.6,5017.5
Exp/Cntr=0.3,0.1

Type RM Length L Ch R = 1,693,195,195,195
BEGIN DESCRIPTION:
Mapping XS 86e8b24b
END DESCRIPTION:
XS GIS Cut Line= 4
      2782067.64     10173278.55      2781942.13     10172902.02
      2781700.75     10172771.67      2781584.86     10172728.21
#Sta/Elev= 30
  4501.3 1303.44  4517.6 1302.92  4528.3 1303.68  4549.2 1303.22  4591.6 1303.99
  4681.2 1303.01  4707.3 1303.67  4813.0 1301.98  4903.1 1301.80  4908.8 1302.58
  4925.0 1296.92  4939.6 1295.28  5004.4 1292.43  5004.8 1291.93  5009.3 1292.43
  5087.4 1294.03  5100.1 1295.86  5116.3 1301.04  5138.2 1301.58  5154.4 1303.24
  5172.5 1303.84  5177.6 1305.44  5183.0 1304.90  5188.6 1306.28  5199.3 1307.33
  5213.2 1307.85  5238.2 1311.78  5243.5 1311.30  5252.7 1312.34  5296.3 1312.62
#Mann=3,-1,0
  4501.3    0.05       0  5004.4    0.03       0  5009.3    0.05       0
Bank Sta=5004.4,5009.3
Exp/Cntr=0.3,0.1

Type RM Length L Ch R = 1,498,462,462,462
BEGIN DESCRIPTION:
Mapping XS 250ea424
END DESCRIPTION:
XS GIS Cut Line= 4
      2782088.98     10173200.44      2782081.17     10172837.14
      2781874.13     10172645.73      2781573.37     10172609.28
#Sta/Elev= 30
  4464.9 1303.40  4692.3 1301.80  4742.3 1302.11  4792.3 1300.88  4856.2 1301.44
  4863.1 1300.66  4870.4 1297.91  4877.2 1293.83  4891.4 1292.17  4969.6 1292.41
  5009.7 1290.66  5010.1 1290.16  5014.3 1290.16  5014.6 1290.66  5026.3 1291.86
  5033.2 1294.54  5040.0 1295.55  5054.1 1295.95  5068.3 1298.61  5075.7 1301.10
  5168.8 1300.13  5189.3 1301.16  5219.5 1300.26  5269.8 1302.08  5290.0 1305.73
  5300.1 1305.92  5310.1 1304.93  5350.4 1307.14  5380.7 1309.75  5413.2 1310.08
#Mann=3,-1,0
  4464.9    0.05       0  5009.7    0.03       0  5014.6    0.05       0
Bank Sta=5009.7,5014.6
Exp/Cntr=0.3,0.1

Type RM Length L Ch R = 1,36,0,0,0
BEGIN DESCRIPTION:
SANDY 17 1.0
END DESCRIPTION:
XS GIS Cut Line= 4
      2782128.81     10173124.85      2782311.20     10172551.98
      2782194.58     10172329.44      2781315.66     10172359.84
#Sta/Elev= 30
  4282.5 1302.59  4310.4 1302.29  4373.5 1301.26  4482.5 1300.23  4599.2 1301.77
  4830.0 1300.38  4879.6 1299.35  4882.9 1298.29  4893.7 1299.43  4902.9 1298.20
  4916.3 1292.92  4938.9 1287.32  4991.1 1287.67  5048.8 1286.23  5049.3 1285.73
  5054.6 1286.23  5063.1 1288.58  5092.0 1289.83  5135.0 1289.72  5163.9 1298.22
  5173.9 1299.46  5283.9 1300.06  5388.3 1298.84  5494.1 1298.49  5604.1 1299.97
  5704.2 1303.15  5784.2 1302.10  5894.3 1308.18  5981.9 1309.92  6014.4 1310.74
#Mann=8,-1,0
  4282.5    0.05       0  4310.4    0.12       0  4373.5    0.05       0
  5048.8    0.05       0  5054.6    0.05       0  5092.0    0.12       0
  5388.3    0.05       0  5981.9    0.12       0
Bank Sta=5048.8,5054.6
Exp/Cntr=0.3,0.1

Chan Stop Cuts=-1