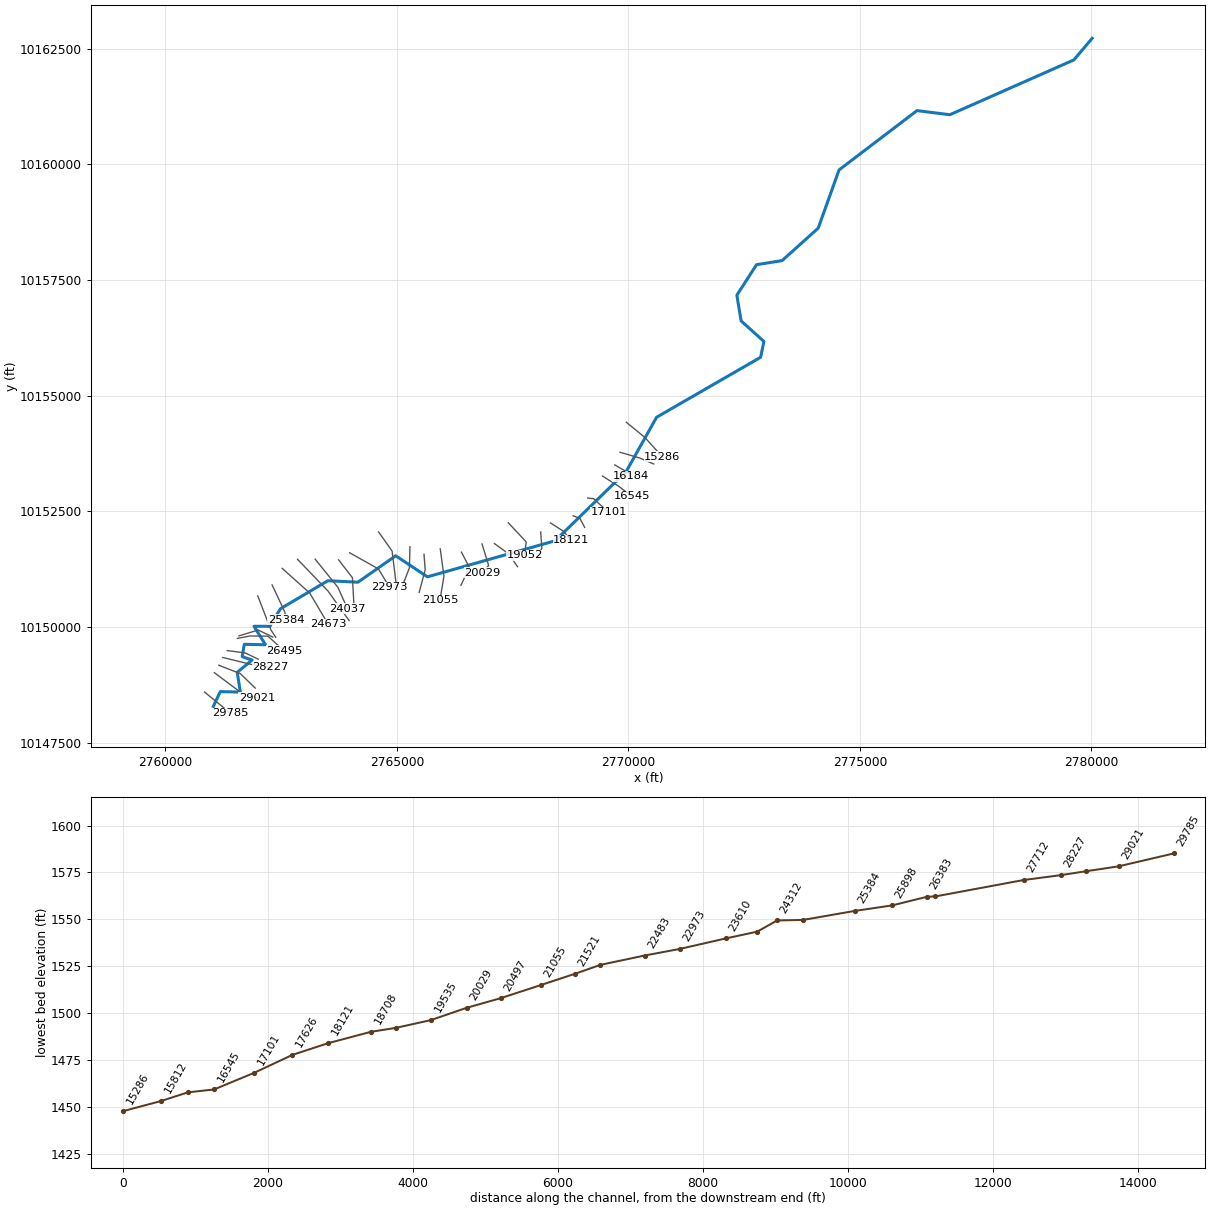
--- WALNUT SPRING CREEK.prj (project) ---

Proj Title=WALNUT SPRING CREEK Base Level Engineering
Current Plan=p01
Default Exp/Contr=0.3,0.1
English Units
Geom File=g01
Flow File=f01
Plan File=p01
Y Axis Title=Elevation
X Axis Title(PF)=Main Channel Distance
X Axis Title(XS)=Station
BEGIN DESCRIPTION:
WALNUT SPRING CREEK
END DESCRIPTION:
DSS Export Rating Curves= 0
DSS Export Rating Curve Sorted= 0
DSS Export Volume Flow Curves= 0
DXF OffsetX= 0
DXF OffsetY= 0
DXF ScaleX= 1
DXF ScaleY= 10

--- WALNUT SPRING CREEK.p01 (plan) ---

Plan Title=Multiple Run
Short Identifier=Multiple
Geom File=g01
Flow File=f01
Subcritical Flow
K Sum by GR= 0
Std Step Tol= 0.01
Critical Tol= 0.01
Num of Std Step Trials= 20
Max Error Tol= 0.3
Flow Tol Ratio= 0.001
Split Flow NTrial= 30
Split Flow Tol= 0.02
Split Flow Ratio= 0.02
Log Output Level= 0
Friction Slope Method= 1
Unsteady Friction Slope Method= 2
Unsteady Bridges Friction Slope Method= 1
Parabolic Critical Depth
Global Vel Dist=  1 , 1 , 1
Global Log Level= 0
CheckData=True
Encroach Param= -1, 0, 0, 0
BEGIN DESCRIPTION:
Multiple Run
END DESCRIPTION:

--- WALNUT SPRING CREEK.f01 (steady flow) ---

Flow Title=Multiple
Number of Profiles=7
Profile Names=10-year,25-year,50-year,1pct_min,100-year,1pct_plu,500-year
River Rch & RM= WALNUT SPRING CR,Reach-1,29785
     754    1266    1809    1297    2469    4700    3402
River Rch & RM= WALNUT SPRING CR,Reach-1,24312
    1065    1837    2772    1920    3857    7746    5355
River Rch & RM= WALNUT SPRING CR,Reach-1,17101
    1164    2016    3140    2187    4393    8822    6104
River Rch & RM= WALNUT SPRING CR,Reach-1,16545
    1652    2923    4832    3334    6868   14151    9554
River Rch & RM= WALNUT SPRING CR,Reach-1,9870
    1978    3543    6119    4196    8792   18422   12276
River Rch & RM= WALNUT SPRING CR,Reach-1,5037
    2238    4047    7082    4800   10240   21846   14328
Boundary for River Rch & Prof#=WALNUT SPRING CR,Reach-1,1
Up Type=0
Dn Type=3
Dn Slope=0.005
Boundary for River Rch & Prof#=WALNUT SPRING CR,Reach-1,2
Up Type=0
Dn Type=3
Dn Slope=0.005
Boundary for River Rch & Prof#=WALNUT SPRING CR,Reach-1,3
Up Type=0
Dn Type=3
Dn Slope=0.005
Boundary for River Rch & Prof#=WALNUT SPRING CR,Reach-1,4
Up Type=0
Dn Type=3
Dn Slope=0.005
Boundary for River Rch & Prof#=WALNUT SPRING CR,Reach-1,5
Up Type=0
Dn Type=3
Dn Slope=0.005
Boundary for River Rch & Prof#=WALNUT SPRING CR,Reach-1,6
Up Type=0
Dn Type=3
Dn Slope=0.005
Boundary for River Rch & Prof#=WALNUT SPRING CR,Reach-1,7
Up Type=0
Dn Type=3
Dn Slope=0.005

--- WALNUT SPRING CREEK.g01 (geometry) ---

Geom Title=Existing Conditions
Program Version=4.10

River Reach=WALNUT SPRING CR,Reach-1
Reach XY= 30
        2761036.       10148283.      2761184.25       10148603.
      2761618.75       10148593.      2761552.25       10149020.
        2761873.       10149287.       2761658.5       10149358.
      2761704.25       10149625.       2762162.5       10149616.
       2761912.5       10150016.        2762256.       10150014.
        2762483.       10150393.        2763508.       10150999.
        2764158.       10150968.      2764973.75       10151539.
      2765659.75       10151084.      2768417.75       10151863.
       2769952.5       10153360.      2770609.25       10154533.
      2772854.75       10155828.      2772927.75       10156171.
        2772435.       10156615.        2772343.       10157171.
       2772768.5       10157830.       2773321.5       10157919.
      2774100.25       10158620.      2774550.25       10159878.
       2776233.5       10161160.       2776943.5       10161071.
      2779622.75       10162256.       2780016.5       10162722.

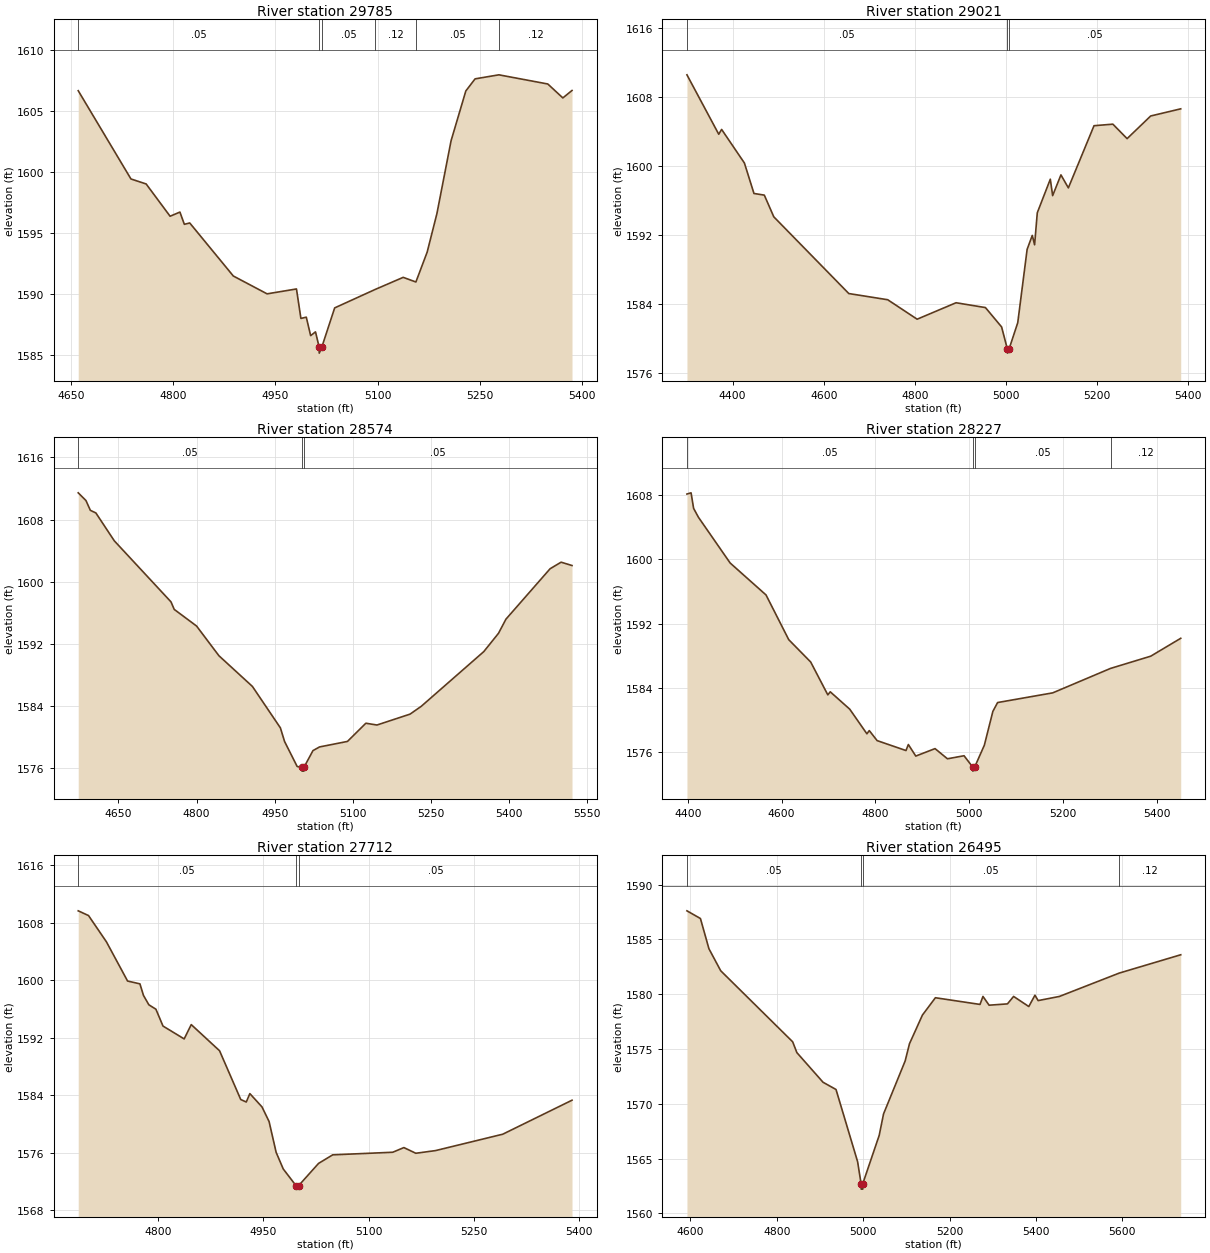
Type RM Length L Ch R = 1 ,29785   ,764,764,764
BEGIN DESCRIPTION:
WALNUT SPRING CREEK 62.0
END DESCRIPTION:
XS GIS Cut Line= 3
      2760846.13     10148593.17      2761221.74     10148286.78
      2761404.87     10148132.78
#Sta/Elev= 30
  4660.8 1606.64  4738.1 1599.42  4760.4 1599.01  4795.5 1596.37  4809.9 1596.71
  4816.4 1595.71  4824.3 1595.82  4888.2 1591.48  4937.7 1590.02  4980.8 1590.42
  4987.3 1588.01  4995.2 1588.11  5001.6  1586.6  5008.7 1586.91    5014 1585.67
  5014.2 1585.17    5018 1585.67  5036.8 1588.87  5096.2 1590.38  5137.3 1591.37
  5155.9 1590.99  5172.4 1593.43  5186.7 1596.58  5207.5 1602.55  5229.1 1606.62
  5242.7 1607.61  5277.6 1607.94  5349.3 1607.19  5371.4 1606.05  5384.8 1606.66
#Mann= 6 ,-1 , 0
  4660.8     .05       0    5014     .05       0    5018     .05       0
  5096.2     .12       0  5155.9     .05       0  5277.6     .12       0
Bank Sta=5014,5018
XS Rating Curve= 0 ,0
Exp/Cntr=0.3,0.1

Type RM Length L Ch R = 1 ,29021   ,447,447,447
BEGIN DESCRIPTION:
WALNUT SPRING CREEK 61.0
END DESCRIPTION:
XS GIS Cut Line= 3
      2761058.06     10149012.44      2761659.54     10148560.82
      2761979.22     10148472.91
#Sta/Elev= 30
  4299.8 1610.58  4369.6 1603.68  4375.9 1604.24  4425.9 1600.34  4446.9  1596.8
  4469.6 1596.61  4490.4 1594.09    4655 1585.18  4740.4 1584.46    4805  1582.2
  4890.4 1584.11  4954.9 1583.55  4990.4  1581.3  5002.9 1578.76  5003.2 1578.26
  5006.9 1578.76  5025.8 1581.79  5046.4 1590.31  5057.7 1591.93  5062.8 1590.84
  5068.7 1594.56  5097.3 1598.46  5102.4 1596.55  5120.6 1598.96  5136.9 1597.45
  5193.2 1604.67  5234.6 1604.85  5265.8 1603.17  5317.6  1605.8  5383.5 1606.63
#Mann= 3 ,-1 , 0
  4299.8     .05       0  5002.9     .05       0  5006.9     .05       0
Bank Sta=5002.9,5006.9
XS Rating Curve= 0 ,0
Exp/Cntr=0.3,0.1

Type RM Length L Ch R = 1 ,28574   ,347,347,347
BEGIN DESCRIPTION:
WALNUT SPRING CREEK 60.0
END DESCRIPTION:
XS GIS Cut Line= 3
      2761153.97      10149172.3      2761617.58     10148992.45
      2761940.96     10148679.05
#Sta/Elev= 30
  4572.8 1611.45  4587.6 1610.46  4596.1  1609.2  4606.7 1608.86    4642 1605.28
  4750.9 1597.42    4757 1596.46  4799.9 1594.32  4842.8  1590.5  4907.1 1586.55
  4960.8 1581.22  4968.8 1579.47    4993 1576.25  5002.1 1576.16  5002.3 1575.66
  5005.8 1575.66  5006.1 1576.16  5023.3  1578.3  5035.9 1578.77  5089.5 1579.48
  5124.8 1581.82  5146.1 1581.59  5209.6 1582.99    5231 1583.99  5351.1 1591.03
  5379.4 1593.39  5393.6  1595.2  5478.4 1601.69  5499.5 1602.53  5520.4  1602.1
#Mann= 3 ,-1 , 0
  4572.8     .05       0  5002.1     .05       0  5006.1     .05       0
Bank Sta=5002.1,5006.1
XS Rating Curve= 0 ,0
Exp/Cntr=0.3,0.1

Type RM Length L Ch R = 1 ,28227   ,515,515,515
BEGIN DESCRIPTION:
WALNUT SPRING CREEK 59.0
END DESCRIPTION:
XS GIS Cut Line= 3
      2761241.88     10149340.15      2761857.71     10149189.58
      2762271.86      10149128.5
#Sta/Elev= 30
  4398.4 1608.17  4407.2 1608.32  4412.6 1606.38  4422.9 1605.27  4490.5 1599.56
    4567 1595.57  4615.4 1589.99  4662.2  1587.2  4698.7  1583.1  4703.9 1583.48
  4745.5 1581.31    4782 1578.24  4787.1 1578.64  4803.8 1577.39  4865.3 1576.15
  4870.4  1576.9  4886.2 1575.46  4927.3 1576.39  4953.7 1575.12  4989.1  1575.5
  5007.7 1574.08  5007.9 1573.58  5011.7 1574.08  5032.4 1576.82  5050.5 1581.03
  5060.6 1582.14  5178.2 1583.35  5301.3  1586.4  5387.1 1587.93    5451 1590.16
#Mann= 4 ,-1 , 0
  4398.4     .05       0  5007.7     .03       0  5011.7     .05       0
  5301.3     .12       0
Bank Sta=5007.7,5011.7
XS Rating Curve= 0 ,0
Exp/Cntr=0.3,0.1

Type RM Length L Ch R = 1 ,27712   ,1217,1217,1217
BEGIN DESCRIPTION:
WALNUT SPRING CREEK 58.0
END DESCRIPTION:
XS GIS Cut Line= 3
      2761335.86     10149490.01      2761727.48     10149438.06
      2762005.72      10149303.1
#Sta/Elev= 30
  4685.8 1609.69  4700.5 1609.03    4726 1605.38  4756.2 1599.92  4773.8 1599.53
  4778.9 1597.92  4786.5 1596.62  4796.6    1596  4806.7 1593.66  4836.9 1591.87
    4847 1593.86  4887.4 1590.22  4917.6 1583.44  4925.5 1583.09  4930.6 1584.26
  4947.9 1582.41    4958 1580.38  4968.1 1576.09  4978.2 1573.78  4996.3 1571.47
  4996.6 1570.97  5000.3 1571.47  5028.6 1574.55  5048.8 1575.74  5134.4  1576.1
  5150.3 1576.75  5167.3 1575.96  5195.4 1576.33  5291.3 1578.61  5390.1 1583.34
#Mann= 3 ,-1 , 0
  4685.8     .05       0  4996.3     .03       0  5000.3     .05       0
Bank Sta=4996.3,5000.3
XS Rating Curve= 0 ,0
Exp/Cntr=0.3,0.1

Type RM Length L Ch R = 1 ,26495   ,112,112,112
BEGIN DESCRIPTION:
WALNUT SPRING CREEK 57.0
END DESCRIPTION:
XS GIS Cut Line= 6
      2761555.67     10149753.11      2761831.39     10149805.74
      2762215.06     10149801.74      2762506.81     10149535.98
       2762512.8     10149535.98      2762568.78       10149482.
#Sta/Elev= 30
  4592.2 1587.61  4623.4 1586.91  4643.1 1584.15  4670.4 1582.14  4836.9 1575.66
  4846.7 1574.67  4907.2 1571.97  4937.2 1571.31  4987.2 1564.72  4995.2 1562.72
  4995.5 1562.22    4999 1562.22  4999.2 1562.72  5037.2 1567.13  5047.2 1569.08
  5097.2 1573.91  5107.2 1575.48  5137.2  1578.1  5167.2 1579.68  5270.5 1579.07
  5277.3  1579.8  5291.5    1579    5334 1579.12  5348.2  1579.8  5383.4 1578.88
  5397.6 1579.91    5405 1579.42  5454.3  1579.8  5592.7 1581.93    5735  1583.6
#Mann= 4 ,-1 , 0
  4592.2     .05       0  4995.2     .05       0  4999.2     .05       0
  5592.7     .12       0
Bank Sta=4995.2,4999.2
XS Rating Curve= 0 ,0
Exp/Cntr=0.3,0.1

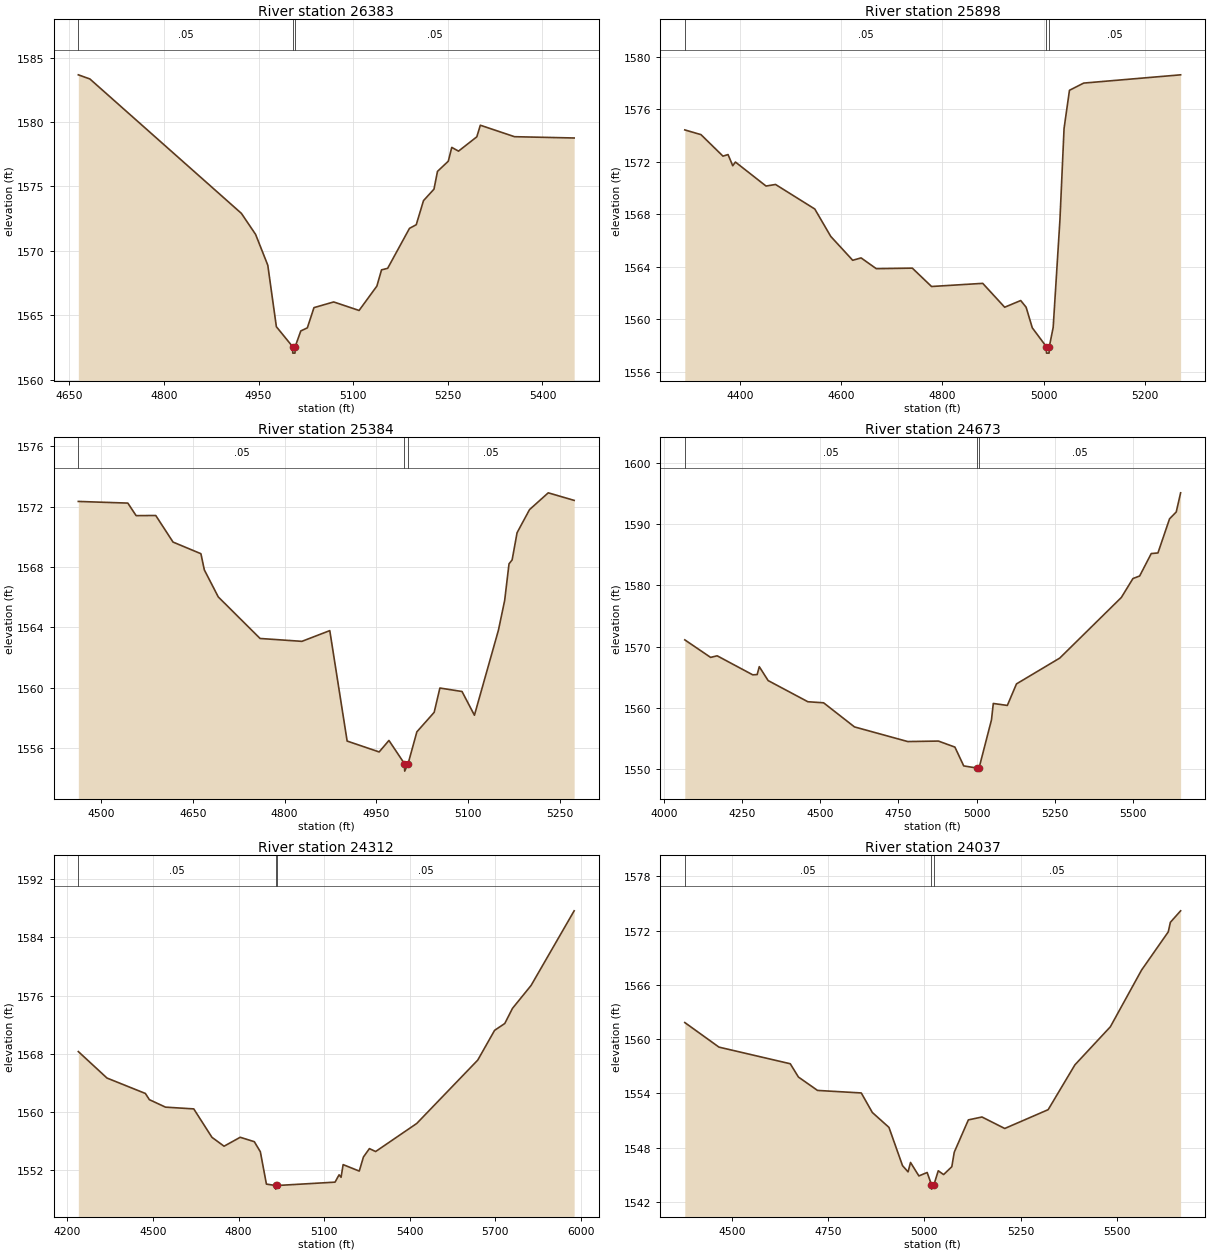
Type RM Length L Ch R = 1 ,26383   ,485,485,485
BEGIN DESCRIPTION:
WALNUT SPRING CREEK 56.0
END DESCRIPTION:
XS GIS Cut Line= 3
      2761588.17     10149807.96      2762004.86     10149933.77
      2762320.86     10149781.82
#Sta/Elev= 30
  4664.3 1583.66  4682.6 1583.34  4922.8 1572.91  4945.3 1571.28  4964.6 1568.89
  4978.2 1564.12    5004 1562.57  5004.2 1562.07  5007.7 1562.07    5008 1562.57
  5016.9 1563.79  5027.3 1564.03  5037.8  1565.6  5069.1 1566.04  5109.3 1565.38
  5137.5 1567.27  5144.9 1568.53  5154.6 1568.65  5189.2 1571.75  5199.9 1572.03
  5211.4  1573.9    5228 1574.79  5233.6 1576.17  5250.7 1576.96  5256.2 1578.03
  5266.9 1577.74  5295.9 1578.85  5301.5 1579.75  5355.7 1578.86  5450.2 1578.76
#Mann= 3 ,-1 , 0
  4664.3     .05       0    5004     .03       0    5008     .05       0
Bank Sta=5004,5008
XS Rating Curve= 0 ,0
Exp/Cntr=0.3,0.1

Type RM Length L Ch R = 1 ,25898   ,514,514,514
BEGIN DESCRIPTION:
WALNUT SPRING CREEK 55.0
END DESCRIPTION:
XS GIS Cut Line= 3
      2761995.27     10150672.95      2762279.01     10149935.63
      2762384.14     10149776.93
#Sta/Elev= 30
  4290.5 1574.44  4322.5 1574.08    4366 1572.44    4376 1572.56  4385.3 1571.71
  4390.6 1571.99  4451.1 1570.16  4469.9 1570.28  4547.5 1568.41  4579.1 1566.32
  4622.5  1564.5  4639.1 1564.68  4669.1 1563.86  4740.4  1563.9  4778.4  1562.5
  4879.6 1562.74    4923 1560.92  4954.7 1561.43  4965.4 1560.92  4977.6 1559.35
  5005.2 1557.92  5005.7 1557.42  5010.8 1557.42  5011.3 1557.92  5018.9 1559.38
  5032.3  1567.6  5040.4 1574.54  5051.1 1577.46  5079.2 1578.01  5270.9 1578.64
#Mann= 3 ,-1 , 0
  4290.5     .05       0  5005.2     .05       0  5011.3     .05       0
Bank Sta=5005.2,5011.3
XS Rating Curve= 0 ,0
Exp/Cntr=0.3,0.1

Type RM Length L Ch R = 1 ,25384   ,711,711,711
BEGIN DESCRIPTION:
WALNUT SPRING CREEK 54.0
END DESCRIPTION:
XS GIS Cut Line= 3
      2762304.99     10150908.76      2762578.75     10150325.29
      2762610.71     10150161.48
#Sta/Elev= 30
  4462.5 1572.34  4543.5 1572.23  4557.1  1571.4  4589.2 1571.41  4617.5 1569.65
  4663.1 1568.88  4668.7 1567.81  4691.5 1566.02  4759.9 1563.27  4828.4 1563.08
    4874 1563.79  4902.4 1556.48  4954.8 1555.76  4970.8 1556.52  4996.1 1554.99
  4996.6 1554.49  5002.2 1554.99  5016.5 1557.09  5044.8 1558.38  5054.2 1559.99
  5090.4 1559.76  5110.7 1558.19    5150 1563.82  5160.2 1565.79  5167.3 1568.21
  5172.4 1568.47  5180.5 1570.27  5200.9  1571.8  5231.5 1572.91  5273.9 1572.41
#Mann= 3 ,-1 , 0
  4462.5     .05       0  4996.1     .03       0  5002.2     .05       0
Bank Sta=4996.1,5002.2
XS Rating Curve= 0 ,0
Exp/Cntr=0.3,0.1

Type RM Length L Ch R = 1 ,24673   ,361,361,361
BEGIN DESCRIPTION:
WALNUT SPRING CREEK 53.0
END DESCRIPTION:
XS GIS Cut Line= 3
      2762522.78     10151266.49      2763116.76     10150734.12
      2763518.01     10150056.44
#Sta/Elev= 30
  4067.2 1571.09  4149.8 1568.23  4170.7 1568.49  4284.4 1565.39  4298.6 1565.43
  4305.3 1566.72  4333.7 1564.45  4460.8    1561  4510.9 1560.83  4609.6  1556.9
    4780 1554.51    4878 1554.59  4930.7 1553.61    4959 1550.54  5001.6 1550.19
  5002.1 1549.69  5007.9 1550.19  5047.7 1558.05  5053.5 1560.72  5098.4  1560.4
  5127.6 1563.91    5266 1568.12  5462.9    1578    5500 1581.09  5521.4  1581.5
  5558.5 1585.16  5579.9 1585.26    5617 1590.82  5638.4 1591.94  5652.4 1595.06
#Mann= 3 ,-1 , 0
  4067.2     .05       0  5001.6     .05       0  5007.9     .05       0
Bank Sta=5001.6,5007.9
XS Rating Curve= 0 ,0
Exp/Cntr=0.3,0.1

Type RM Length L Ch R = 1 ,24312   ,275,275,275
BEGIN DESCRIPTION:
WALNUT SPRING CREEK 52.0
END DESCRIPTION:
XS GIS Cut Line= 3
      2762853.05     10151462.68      2763514.56     10150774.35
      2763969.44     10150136.62
#Sta/Elev= 30
  4238.5  1568.3    4339 1564.66  4473.6 1562.54  4487.5 1561.69  4544.1 1560.66
  4643.1 1560.42  4706.9 1556.51  4749.4 1555.29    4806 1556.52  4855.4 1555.91
  4876.5 1554.53  4897.8 1550.08  4929.8 1549.89  4930.3 1549.39  4936.3 1549.89
  5138.4 1550.35  5152.5 1551.36  5159.5 1551.02  5166.7 1552.76  5223.2 1551.87
  5237.9 1553.81  5258.8 1554.96  5280.7 1554.56  5424.8 1558.42  5638.6 1567.13
  5697.6 1571.22  5733.3 1572.16  5760.3 1574.24  5825.5 1577.39  5976.5 1587.65
#Mann= 3 ,-1 , 0
  4238.5     .05       0  4929.8     .05       0  4936.3     .05       0
Bank Sta=4929.8,4936.3
XS Rating Curve= 0 ,0
Exp/Cntr=0.3,0.1

Type RM Length L Ch R = 1 ,24037   ,427,427,427
BEGIN DESCRIPTION:
WALNUT SPRING CREEK 51.0
END DESCRIPTION:
XS GIS Cut Line= 3
      2763234.18     10151466.29      2763725.75     10150856.83
       2763932.9     10150396.71
#Sta/Elev= 30
  4377.9 1561.84  4466.7 1559.12  4651.8 1557.28    4673 1555.81  4722.6 1554.33
  4836.2 1554.05  4864.9 1551.89  4908.1 1550.24  4943.3 1546.01  4957.7 1545.32
  4964.1 1546.36  4985.8 1544.87  5007.3 1545.25  5018.4 1543.91  5018.9 1543.41
  5024.9 1543.91  5036.1 1545.44    5050 1545.02  5071.3 1545.89  5077.7  1547.5
  5114.3 1551.07  5149.6 1551.39  5208.8 1550.12  5321.5  1552.2    5391 1557.16
    5483 1561.37    5564 1567.64  5633.4 1571.87  5638.9 1572.93  5665.5  1574.2
#Mann= 3 ,-1 , 0
  4377.9     .05       0  5018.4     .05       0  5024.9     .05       0
Bank Sta=5018.4,5024.9
XS Rating Curve= 0 ,0
Exp/Cntr=0.3,0.1

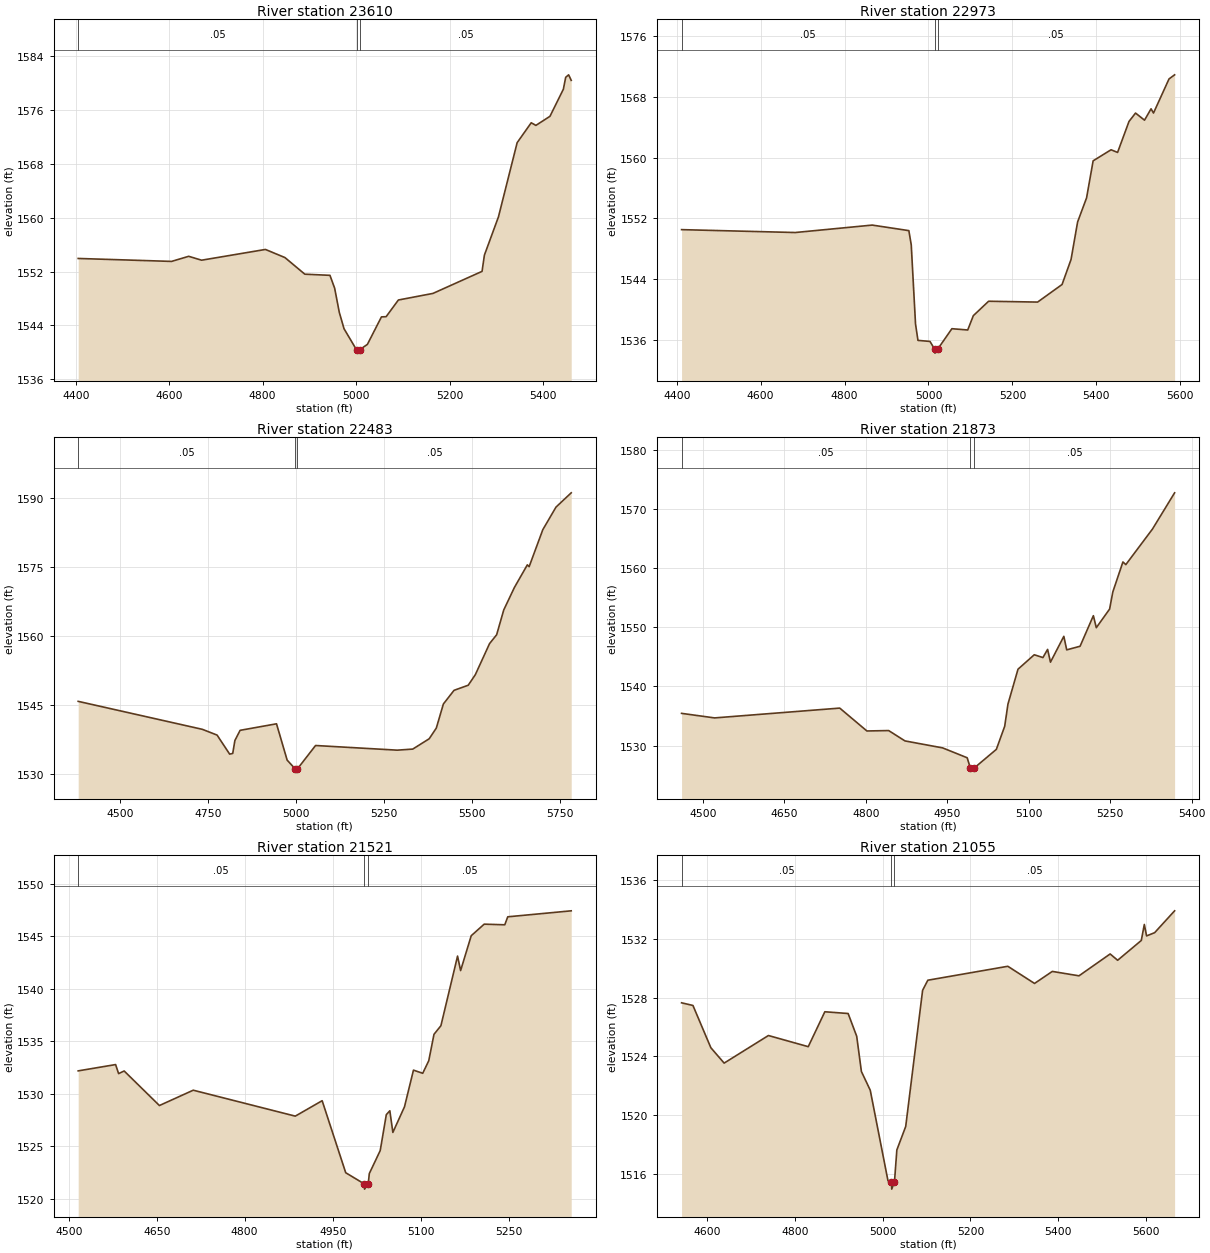
Type RM Length L Ch R = 1 ,23610   ,637,637,637
BEGIN DESCRIPTION:
WALNUT SPRING CREEK 50.0
END DESCRIPTION:
XS GIS Cut Line= 3
      2763741.75     10151450.29      2764039.48     10151064.65
      2764071.42     10150497.64
#Sta/Elev= 30
  4405.3 1553.94  4605.1  1553.5  4641.8 1554.26  4669.4 1553.68    4806 1555.28
  4847.8 1554.07  4890.3  1551.6  4944.1 1551.43  4954.1 1549.52  4964.1 1545.92
  4974.2 1543.49  5000.9 1540.36  5001.4 1539.86  5007.5 1540.36  5024.2 1541.16
  5054.3 1545.25  5064.3 1545.28  5090.5 1547.76  5164.5 1548.74  5269.6 1552.02
  5274.6 1554.43  5304.7 1560.13  5344.7 1571.16  5374.8 1574.12  5384.8 1573.73
  5414.9 1575.08  5443.6 1579.11  5448.6 1580.88  5454.9 1581.25  5460.4 1580.43
#Mann= 3 ,-1 , 0
  4405.3     .05       0  5000.9     .05       0  5007.5     .05       0
Bank Sta=5000.9,5007.5
XS Rating Curve= 0 ,0
Exp/Cntr=0.3,0.1

Type RM Length L Ch R = 1 ,22973   ,490,490,490
BEGIN DESCRIPTION:
WALNUT SPRING CREEK 49.0
END DESCRIPTION:
XS GIS Cut Line= 3
      2763979.54     10151604.17      2764602.62     10151253.87
      2764838.81     10150858.79
#Sta/Elev= 30
  4411.5 1550.51  4682.4 1550.13    4866 1551.11  4953.2 1550.38  4958.9 1548.51
  4969.1 1538.07  4974.9 1535.91  5003.6 1535.77  5014.9 1534.73  5015.4 1534.23
  5021.6 1534.73  5055.8 1537.45  5093.5 1537.28  5106.9 1539.17  5143.3 1541.07
  5260.1 1540.96  5318.4 1543.28  5339.8 1546.58  5355.4 1551.52  5376.8  1554.7
  5392.4 1559.58  5435.1 1561.04  5450.7 1560.69  5477.9 1564.77  5493.5 1565.88
  5514.9 1564.94  5530.5 1566.44  5536.3 1565.88  5573.3 1570.38  5586.6 1570.92
#Mann= 3 ,-1 , 0
  4411.5     .05       0  5014.9     .05       0  5021.6     .05       0
Bank Sta=5014.9,5021.6
XS Rating Curve= 0 ,0
Exp/Cntr=0.3,0.1

Type RM Length L Ch R = 1 ,22483   ,610,610,610
BEGIN DESCRIPTION:
WALNUT SPRING CREEK 48.0
END DESCRIPTION:
XS GIS Cut Line= 3
      2764605.69      10152053.1      2764896.73     10151640.15
      2765005.68     10150753.12
#Sta/Elev= 30
  4381.8 1545.81  4734.1 1539.74  4775.9 1538.49  4811.6 1534.36  4820.3 1534.51
  4826.4 1537.31  4841.2 1539.52  4944.5 1540.94  4974.7 1533.06  4997.3 1531.17
  4997.8 1530.67    5004 1531.17  5055.3 1536.23    5287 1535.22    5331 1535.45
  5377.7 1537.69  5397.9 1540.01    5418 1545.24  5448.2  1548.2  5488.5 1549.31
  5508.7 1551.61    5549 1558.34  5569.1 1560.26  5589.3 1565.65  5619.5 1570.52
  5656.2 1575.43  5661.3 1575.03  5700.1 1583.06  5737.5 1587.96  5780.7 1591.06
#Mann= 3 ,-1 , 0
  4381.8     .05       0  4997.3     .05       0    5004     .05       0
Bank Sta=4997.3,5004
XS Rating Curve= 0 ,0
Exp/Cntr=0.3,0.1

Type RM Length L Ch R = 1 ,21873   ,352,352,352
BEGIN DESCRIPTION:
WALNUT SPRING CREEK 47.0
END DESCRIPTION:
XS GIS Cut Line= 3
      2765282.43     10151734.33      2765270.19     10151276.84
      2765107.15     10150857.05
#Sta/Elev= 30
  4460.6 1535.45  4521.4 1534.68  4751.9 1536.34  4801.9 1532.47    4842 1532.54
    4872 1530.79  4941.4 1529.61  4986.6 1527.94  4992.5 1526.18    4993 1525.68
  4999.2 1526.18  5040.3 1529.36  5055.7 1533.27  5061.7 1537.02  5080.2 1542.92
  5110.1 1545.36  5126.1 1544.89  5134.7 1546.27    5140 1544.11  5164.6 1548.48
  5169.9 1546.19  5194.5  1546.8    5219 1551.97  5224.4 1549.94  5248.9 1553.09
  5254.8 1555.98  5273.4 1561.06  5278.8 1560.61  5327.9 1566.63  5368.6 1572.75
#Mann= 3 ,-1 , 0
  4460.6     .05       0  4992.5     .05       0  4999.2     .05       0
Bank Sta=4992.5,4999.2
XS Rating Curve= 0 ,0
Exp/Cntr=0.3,0.1

Type RM Length L Ch R = 1 ,21521   ,466,466,466
BEGIN DESCRIPTION:
WALNUT SPRING CREEK 46.0
END DESCRIPTION:
XS GIS Cut Line= 3
      2765585.89     10151571.26      2765610.91     10151236.04
      2765481.73     10150748.31
#Sta/Elev= 30
  4516.1 1532.17  4579.9 1532.77    4585 1531.91  4594.5 1532.16  4654.6 1528.87
  4712.3 1530.33  4886.3 1527.86  4932.1 1529.33  4972.3 1522.47  5003.9 1521.41
  5004.4 1520.91  5010.7 1521.41  5012.5 1522.39  5031.1 1524.58  5041.5    1528
  5047.5 1528.37  5052.7 1526.31  5072.5 1528.75  5087.8 1532.24  5103.6 1531.94
  5113.9 1533.14  5122.8 1535.65  5134.6 1536.47    5163  1543.1  5168.2 1541.72
  5186.3 1545.04  5208.4 1546.14  5243.5 1546.08  5248.6 1546.84  5356.8 1547.41
#Mann= 3 ,-1 , 0
  4516.1     .05       0  5003.9     .03       0  5010.7     .05       0
Bank Sta=5003.9,5010.7
XS Rating Curve= 0 ,0
Exp/Cntr=0.3,0.1

Type RM Length L Ch R = 1 ,21055   ,558,558,558
BEGIN DESCRIPTION:
WALNUT SPRING CREEK 45.0
END DESCRIPTION:
XS GIS Cut Line= 3
       2765936.6     10151689.25      2766016.45     10151099.02
      2765929.65     10150578.22
#Sta/Elev= 30
  4541.6 1527.65  4567.5 1527.47  4608.3 1524.59  4638.6 1523.54  4739.5 1525.42
  4830.3 1524.66  4868.1 1527.04  4921.2 1526.92  4940.7 1525.37  4951.4 1522.97
  4971.6 1521.69    5012 1515.52    5020 1515.45  5020.5 1514.95  5026.8 1515.45
  5032.2 1517.62  5052.4 1519.22  5090.9  1528.5  5102.8 1529.19  5285.1 1530.14
    5346 1528.97  5386.5 1529.79  5447.3 1529.49  5518.3 1530.98  5535.4 1530.55
  5589.3  1531.9  5596.2 1532.99  5601.3 1532.21  5619.7 1532.43  5665.2 1533.92
#Mann= 3 ,-1 , 0
  4541.6     .05       0    5020     .05       0  5026.8     .05       0
Bank Sta=5020,5026.8
XS Rating Curve= 0 ,0
Exp/Cntr=0.3,0.1

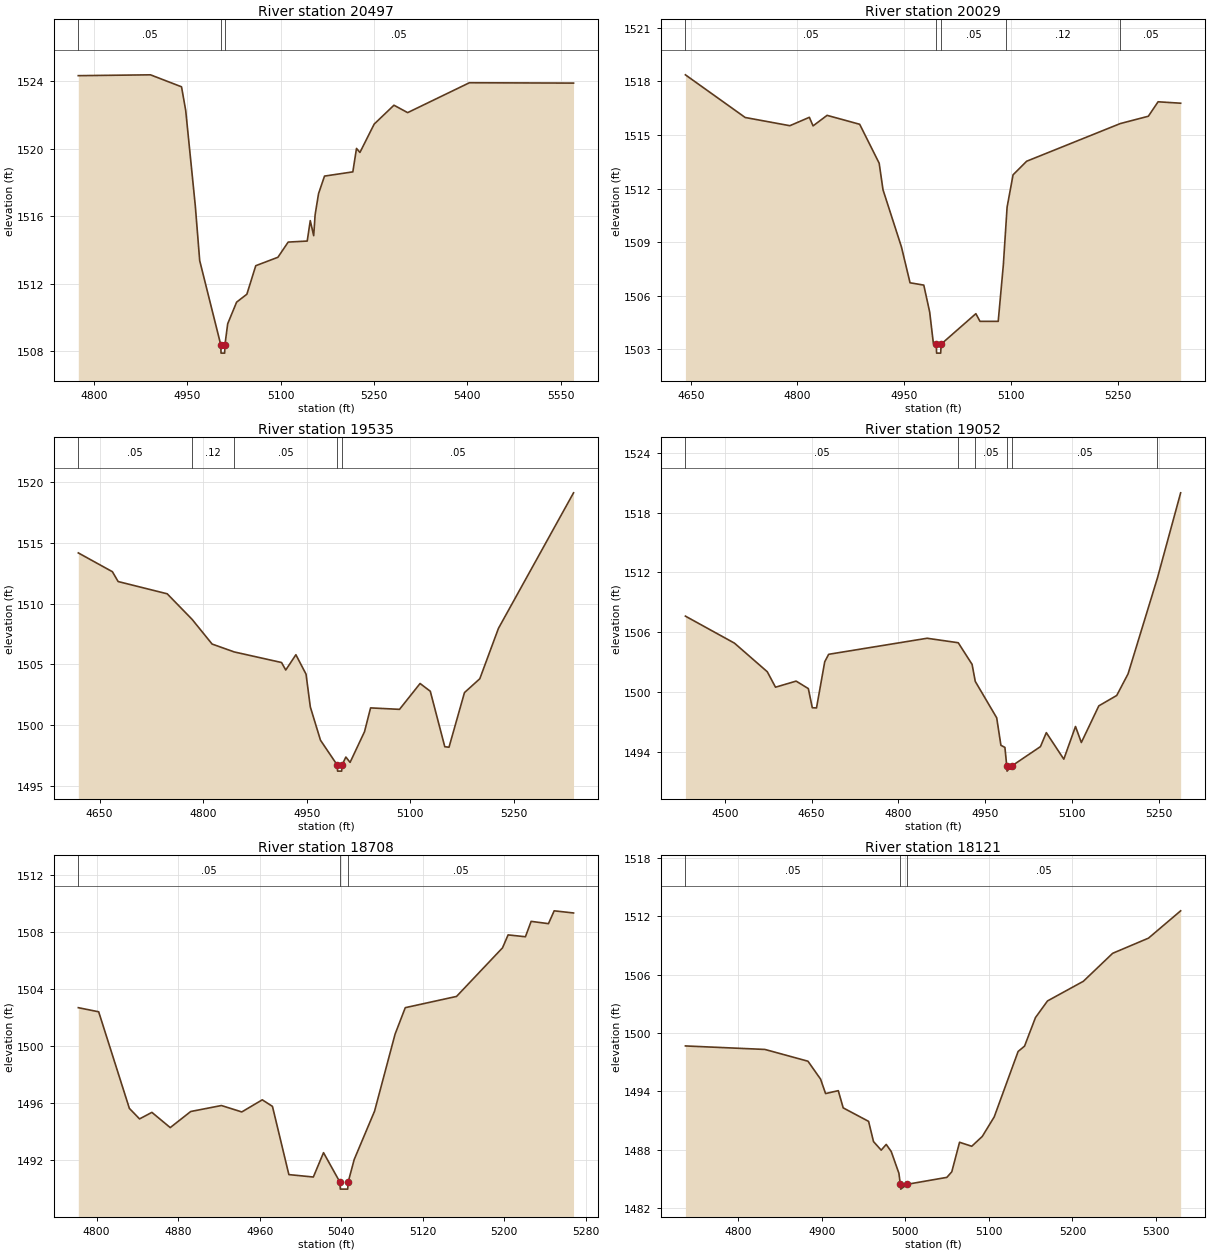
Type RM Length L Ch R = 1 ,20497   ,468,468,468
BEGIN DESCRIPTION:
WALNUT SPRING CREEK 44.0
END DESCRIPTION:
XS GIS Cut Line= 3
      2766394.93     10151616.37      2766564.07      10151289.7
      2766384.52     10150901.14
#Sta/Elev= 30
  4774.8 1524.34  4890.8 1524.39  4940.7 1523.68  4947.4 1522.28  4962.8 1516.64
  4969.9 1513.38  5003.7  1508.4  5004.2  1507.9    5010  1507.9  5010.5  1508.4
  5014.9 1509.64  5029.2 1510.92  5045.7 1511.39    5060 1513.08  5095.6 1513.58
  5112.1 1514.48  5142.7 1514.54  5147.6 1515.75  5153.1 1514.86  5155.4  1516.1
  5160.9 1517.35  5170.5 1518.39    5216 1518.64  5221.9 1520.03  5227.4 1519.79
  5250.3 1521.47  5282.1 1522.59  5304.1 1522.15  5403.3 1523.92  5570.7  1523.9
#Mann= 3 ,-1 , 0
  4774.8     .05       0  5003.7     .05       0  5010.5     .05       0
Bank Sta=5003.7,5010.5
XS Rating Curve= 0 ,0
Exp/Cntr=0.3,0.1

Type RM Length L Ch R = 1 ,20029   ,494,494,494
BEGIN DESCRIPTION:
WALNUT SPRING CREEK 43.0
END DESCRIPTION:
XS GIS Cut Line= 3
      2766839.37     10151793.47      2766981.73     10151328.18
       2766846.3     10151168.45
#Sta/Elev= 30
  4642.5 1518.37  4726.5 1515.98  4789.3 1515.52  4816.7 1515.99  4821.9 1515.51
  4841.6  1516.1  4887.4  1515.6  4914.8 1513.42  4920.2 1511.93  4946.1 1508.73
  4958.2 1506.72  4977.5 1506.59  4985.8 1505.08    4991 1503.32    4995 1503.28
  4995.5 1502.78  5001.3 1502.78  5001.8 1503.28  5050.7 1504.99  5056.5 1504.56
  5082.1 1504.56  5089.3 1507.71  5093.6 1510.35  5094.6 1510.96    5103 1512.77
  5122.1 1513.53  5253.7 1515.64  5293.1 1516.05  5306.8 1516.86  5338.5 1516.78
#Mann= 5 ,-1 , 0
  4642.5     .05       0    4995     .03       0  5001.8     .05       0
  5093.6     .12       0  5253.7     .05       0
Bank Sta=4995,5001.8
XS Rating Curve= 0 ,0
Exp/Cntr=0.3,0.1

Type RM Length L Ch R = 1 ,19535   ,483,483,483
BEGIN DESCRIPTION:
WALNUT SPRING CREEK 42.0
END DESCRIPTION:
XS GIS Cut Line= 3
      2767105.67     10151803.12      2767414.25       10151580.
      2767605.67     10151303.13
#Sta/Elev= 30
  4619.2 1514.19  4668.6 1512.64  4676.9 1511.83    4748 1510.82  4784.1 1508.71
    4813 1506.68  4845.1 1506.03  4913.6 1505.16  4919.7 1504.54  4934.4  1505.8
  4949.1  1504.2  4955.3  1501.5    4970 1498.76  4994.3 1496.71  4994.8 1496.21
  5000.7 1496.21  5001.2 1496.71  5006.8 1497.37  5012.9 1496.93  5033.8 1499.46
  5042.6 1501.42  5084.5  1501.3  5114.3 1503.43  5129.1 1502.79  5150.1 1498.22
  5156.2 1498.18  5178.6 1502.68  5200.8 1503.82  5227.8 1507.97  5336.6 1519.14
#Mann= 5 ,-1 , 0
  4619.2     .05       0  4784.1     .12       0  4845.1     .05       0
  4994.3     .05       0  5001.2     .05       0
Bank Sta=4994.3,5001.2
XS Rating Curve= 0 ,0
Exp/Cntr=0.3,0.1

Type RM Length L Ch R = 1 ,19052   ,344,344,344
BEGIN DESCRIPTION:
WALNUT SPRING CREEK 41.0
END DESCRIPTION:
XS GIS Cut Line= 3
      2767405.69      10152253.1      2767793.25       10151838.
      2767755.68     10151553.07
#Sta/Elev= 30
  4432.1 1507.62  4516.8 1504.91  4573.5 1502.04  4587.7 1500.49  4623.3  1501.1
  4644.4 1500.35  4651.2 1498.43  4658.5 1498.41  4672.7 1503.04  4679.5 1503.79
  4849.5  1505.4  4903.3 1504.95  4927.2 1502.78  4932.7 1501.07  4969.7 1497.42
    4977 1494.66  4983.9 1494.45  4987.1 1492.57  4987.6 1492.07  4995.3 1492.57
  5045.3 1494.53  5055.4 1495.93  5085.6 1493.27  5105.8 1496.55  5115.9 1494.94
  5146.1 1498.62    5177 1499.66  5196.6 1501.83  5247.3 1511.45  5287.4 1519.99
#Mann= 6 ,-1 , 0
  4432.1     .05       0  4903.3     .12       0  4932.7     .05       0
  4987.1     .05       0  4995.3     .05       0  5247.3     .12       0
Bank Sta=4987.1,4995.3
XS Rating Curve= 0 ,0
Exp/Cntr=0.3,0.1

Type RM Length L Ch R = 1 ,18708   ,587,587,587
BEGIN DESCRIPTION:
WALNUT SPRING CREEK 40.0
END DESCRIPTION:
XS GIS Cut Line= 3
      2768105.69      10152053.1      2768131.03     10151703.18
      2768072.02     10151581.69
#Sta/Elev= 30
    4782  1502.7    4802 1502.41  4832.1 1495.63  4842.1 1494.89  4854.2 1495.35
  4872.2 1494.28  4892.3 1495.41  4922.4 1495.83  4942.4 1495.38  4962.5 1496.23
  4972.5 1495.77  4988.6 1490.98  5012.6 1490.81  5022.6 1492.52  5038.6 1490.46
  5039.1 1489.96  5046.3 1489.96  5046.8 1490.46  5052.7 1492.04  5072.7 1495.44
  5092.8 1500.84  5102.8  1502.7  5153.1 1503.49  5198.2  1506.9  5203.7 1507.81
  5220.7 1507.68  5226.3 1508.76  5243.3  1508.6  5248.9  1509.5  5267.9 1509.35
#Mann= 3 ,-1 , 0
    4782     .05       0  5038.6     .05       0  5046.8     .05       0
Bank Sta=5038.6,5046.8
XS Rating Curve= 0 ,0
Exp/Cntr=0.3,0.1

Type RM Length L Ch R = 1 ,18121   ,495,495,495
BEGIN DESCRIPTION:
WALNUT SPRING CREEK 39.0
END DESCRIPTION:
XS GIS Cut Line= 3
      2768318.56     10152248.31       2768602.9     10152065.01
      2768766.43     10151869.88
#Sta/Elev= 30
  4736.7 1498.67  4831.9 1498.31  4883.4  1497.1  4898.5 1495.26  4904.5 1493.77
  4919.7 1494.07  4925.6  1492.3    4956 1490.91  4961.9 1488.83  4971.1 1487.95
  4977.1 1488.54  4983.1 1487.81  4992.3 1485.57    4994 1484.44  4994.5 1483.94
  5002.4 1484.44  5049.7 1485.15  5055.6 1485.72  5064.9 1488.76  5079.5 1488.35
  5092.1 1489.36  5106.4 1491.37    5135  1498.1  5142.7 1498.65  5155.8 1501.59
  5170.2  1503.3  5213.1 1505.32  5248.2  1508.2  5291.1 1509.76  5329.6 1512.57
#Mann= 3 ,-1 , 0
  4736.7     .05       0    4994     .05       0  5002.4     .05       0
Bank Sta=4994,5002.4
XS Rating Curve= 0 ,0
Exp/Cntr=0.3,0.1

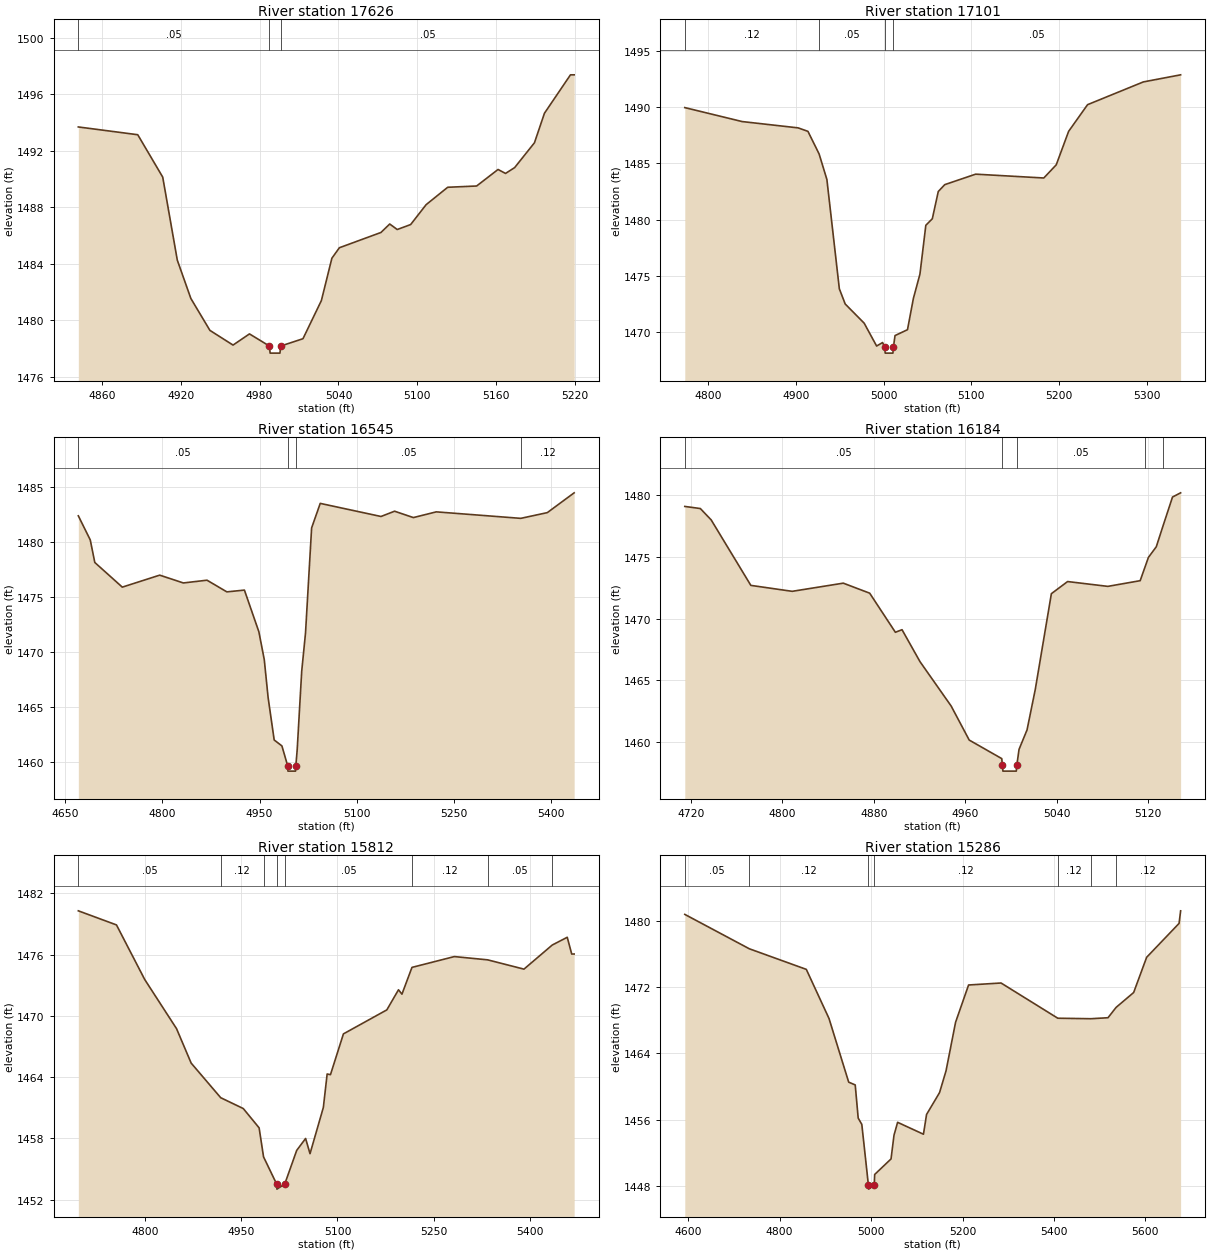
Type RM Length L Ch R = 1 ,17626   ,525,525,525
BEGIN DESCRIPTION:
WALNUT SPRING CREEK 38.0
END DESCRIPTION:
XS GIS Cut Line= 3
      2768805.66     10152403.12      2768953.25       10152347.
      2769055.69      10152153.1
#Sta/Elev= 30
  4842.1 1493.68  4887.3 1493.13  4906.3 1490.13  4917.4 1484.25  4927.7 1481.54
  4942.2 1479.28  4959.8 1478.24  4972.3 1479.03  4987.5 1478.17    4988 1477.67
  4995.5 1477.67    4996 1478.17    5013 1478.69    5027 1481.39    5035 1484.39
  5040.7 1485.13  5072.3 1486.21    5079 1486.81  5084.7 1486.42  5094.9 1486.77
  5106.7 1488.18  5123.1 1489.41  5145.1  1489.5  5161.4 1490.67  5167.1 1490.39
    5174  1490.8  5189.1 1492.56  5196.7 1494.65  5216.5 1497.37  5219.3 1497.37
#Mann= 3 ,-1 , 0
  4842.1     .05       0  4987.5     .05       0    4996     .05       0
Bank Sta=4987.5,4996
XS Rating Curve= 0 ,0
Exp/Cntr=0.3,0.1

Type RM Length L Ch R = 1 ,17101   ,556,556,556
BEGIN DESCRIPTION:
WALNUT SPRING CREEK 37.0
END DESCRIPTION:
XS GIS Cut Line= 3
      2769120.65     10152786.52      2769249.09     10152772.63
        2769571.     10152478.41
#Sta/Elev= 30
  4773.4 1489.94  4838.8  1488.7  4902.6 1488.14  4913.8 1487.83  4926.5 1485.83
  4935.4 1483.56  4949.6 1473.85  4956.3  1472.5  4977.9  1470.8  4992.1 1468.77
  4998.9 1469.08  5001.4 1468.64  5001.9 1468.14  5010.7 1468.14  5011.2 1468.64
  5013.1  1469.7  5027.3 1470.22    5034 1472.99  5041.5 1475.16  5048.2 1479.49
  5055.6 1480.07  5062.4 1482.49  5069.8  1483.1    5105 1484.03  5182.7 1483.69
  5196.9 1484.86    5211 1487.83  5232.6  1490.2  5296.2 1492.22  5338.7 1492.85
#Mann= 4 ,-1 , 0
  4773.4     .12       0  4926.5     .05       0  5001.4     .05       0
  5011.2     .05       0
Bank Sta=5001.4,5011.2
XS Rating Curve= 0 ,0
Exp/Cntr=0.3,0.1

Type RM Length L Ch R = 1 ,16545   ,361,361,361
BEGIN DESCRIPTION:
WALNUT SPRING CREEK 36.0
END DESCRIPTION:
XS GIS Cut Line= 3
       2769440.1     10153262.19      2769787.28     10153043.46
      2770068.52      10152828.2
#Sta/Elev= 30
  4670.6 1482.41    4689 1480.22    4696 1478.17  4738.4 1475.93  4796.1 1477.02
  4832.5 1476.31    4869 1476.56  4899.6  1475.5  4926.7 1475.66    4949 1471.87
  4957.3 1469.34  4963.2 1465.91  4972.6 1462.04  4984.5  1461.5  4993.3 1459.71
  4993.8 1459.21  5005.5 1459.21    5006 1459.71  5008.1 1461.19    5015 1468.27
  5020.9 1471.77  5030.3 1481.31  5043.6 1483.54  5137.3 1482.35  5158.2 1482.83
  5187.2 1482.25  5222.5 1482.77  5352.8 1482.18  5393.7  1482.7  5435.1  1484.5
#Mann= 4 ,-1 , 0
  4670.6     .05       0  4993.3     .05       0    5006     .05       0
  5352.8     .12       0
Bank Sta=4993.3,5006
XS Rating Curve= 0 ,0
Exp/Cntr=0.3,0.1

Type RM Length L Ch R = 1 ,16184   ,372,372,372
BEGIN DESCRIPTION:
WALNUT SPRING CREEK 35.0
END DESCRIPTION:
XS GIS Cut Line= 3
      2769705.69     10153503.11       2769952.5       10153360.
      2770055.71     10153253.09
#Sta/Elev= 30
  4714.7 1479.06  4728.3 1478.89  4737.8 1477.97  4772.5 1472.68  4808.7  1472.2
  4853.4 1472.86  4876.5 1472.05    4899 1468.89  4904.8  1469.1  4920.5 1466.52
  4947.8 1462.93  4963.6 1460.18  4992.1 1458.68  4992.6 1458.17  4993.1 1457.67
  5004.8 1457.67  5005.3 1458.17  5007.2 1459.43  5014.2    1461  5021.4 1464.27
  5035.5 1472.01  5049.7 1472.99  5084.9  1472.6  5113.2 1473.06  5117.2  1474.1
  5120.4 1474.94  5127.3  1475.8    5133 1477.43  5141.5 1479.82  5148.6 1480.16
#Mann= 5 ,-1 , 0
  4714.7     .05       0  4992.6     .03       0  5005.3     .05       0
  5117.2     .12       0    5133     .05       0
Bank Sta=4992.6,5005.3
XS Rating Curve= 0 ,0
Exp/Cntr=0.3,0.1

Type RM Length L Ch R = 1 ,15812   ,526,526,526
BEGIN DESCRIPTION:
WALNUT SPRING CREEK 34.0
END DESCRIPTION:
XS GIS Cut Line= 3
      2769818.49     10153776.11      2770238.67     10153654.57
      2770547.68     10153522.64
#Sta/Elev= 30
  4695.8 1480.28  4755.3  1478.9  4799.4 1473.55    4849 1468.74  4871.8 1465.37
  4917.9 1461.98  4953.1 1460.92  4977.8 1459.03  4984.7 1456.19  5005.1 1453.53
  5005.6 1453.03  5017.8 1453.53  5036.4 1456.82  5050.3 1457.99  5057.2  1456.5
    5078 1461.03  5083.9  1464.3  5089.1 1464.24  5109.3 1468.23    5177 1470.58
  5195.2 1472.55  5200.6 1472.12  5216.2 1474.74  5282.3  1475.8  5334.3 1475.48
  5390.9 1474.57    5435 1476.93  5458.4 1477.69  5465.4 1476.05  5469.2 1476.05
#Mann= 8 ,-1 , 0
  4695.8     .05       0  4917.9     .12       0  4984.7     .05       0
  5005.1     .05       0  5017.8     .05       0  5216.2     .12       0
  5334.3     .05       0    5435     .12       0
Bank Sta=5005.1,5017.8
XS Rating Curve= 0 ,0
Exp/Cntr=0.3,0.1

Type RM Length L Ch R = 1 ,15286   ,357,357,357
BEGIN DESCRIPTION:
WALNUT SPRING CREEK 33.0
END DESCRIPTION:
XS GIS Cut Line= 3
      2769953.94     10154425.42      2770349.78     10154102.49
      2770733.97     10153676.77
#Sta/Elev= 30
  4592.7 1480.82  4733.8 1476.66  4858.4 1474.17    4908 1468.24  4951.1 1460.53
  4965.4 1460.19  4971.9 1456.18  4979.8 1455.42  4994.2 1448.09  4994.7 1447.59
    5007 1448.09  5007.9 1449.36  5043.7 1451.24  5050.2 1454.11  5058.1 1455.67
  5114.6 1454.23  5121.4 1456.62  5149.8 1459.26    5164  1461.9  5184.9 1467.78
  5213.3 1472.28  5284.3 1472.52  5408.4 1468.26  5480.7  1468.2  5518.2 1468.32
  5535.9 1469.57  5574.3 1471.37  5602.7 1475.63  5673.6 1479.73    5677 1481.25
#Mann= 7 ,-1 , 0
  4592.7     .05       0  4733.8     .12       0  4994.2     .05       0
    5007     .12       0  5408.4     .12       0  5480.7     .05       0
  5535.9     .12       0
Bank Sta=4994.2,5007
XS Rating Curve= 0 ,0
Exp/Cntr=0.3,0.1