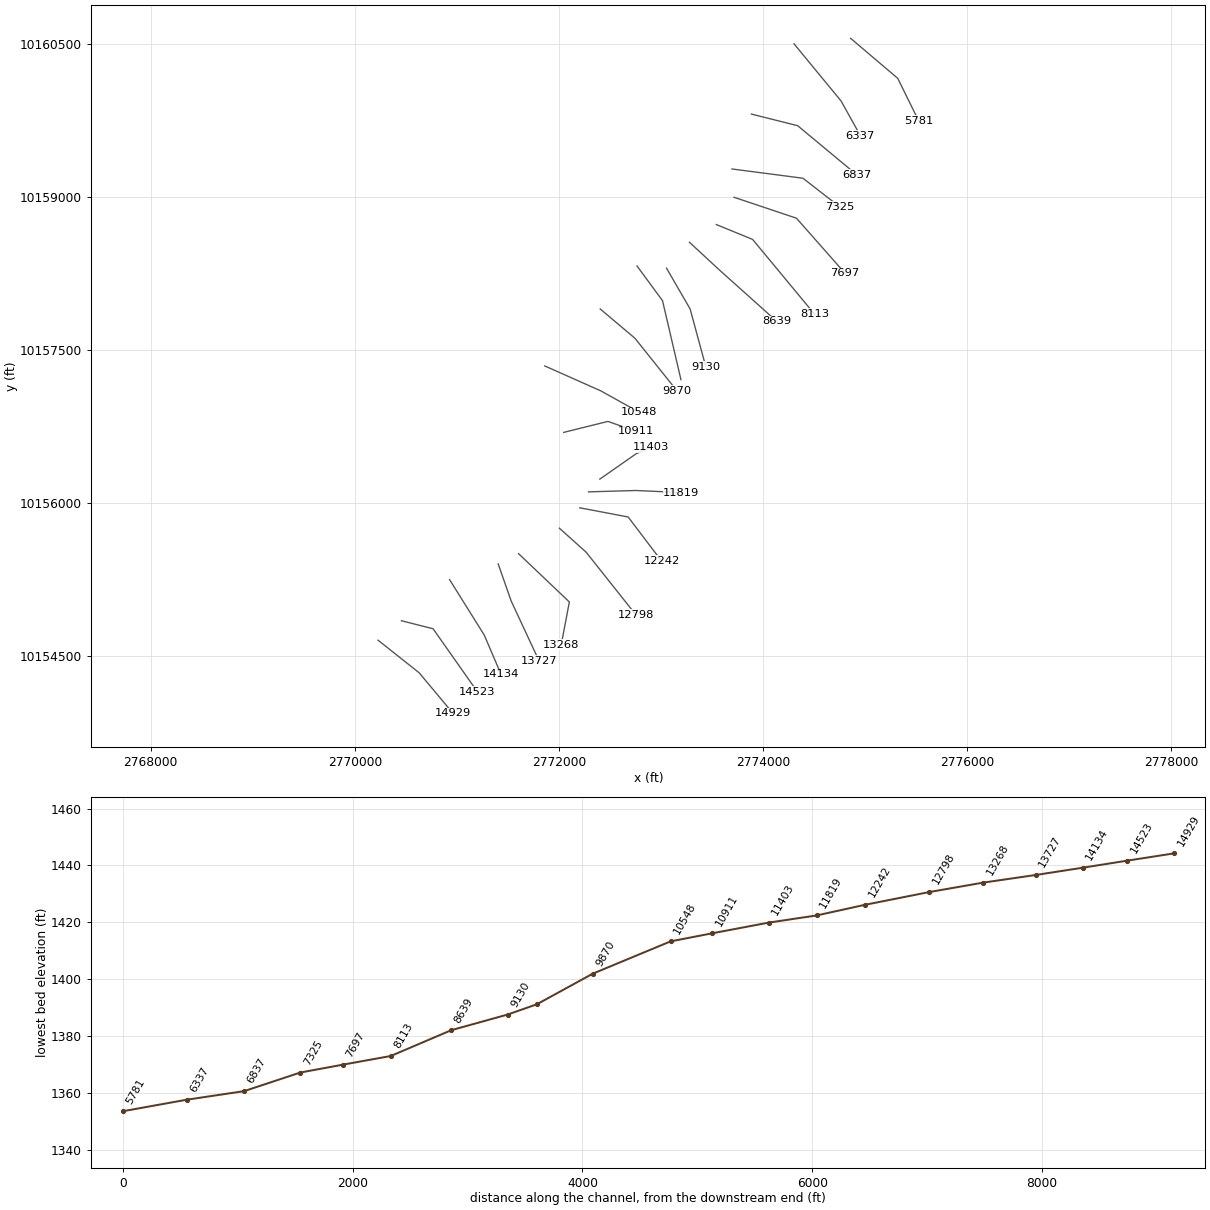
HEC-RAS study WALNUT SPRING CREEK.prj: WALNUT SPRING CREEK Base Level Engineering

--- WALNUT SPRING CREEK.g01 (geometry) --- (continued)

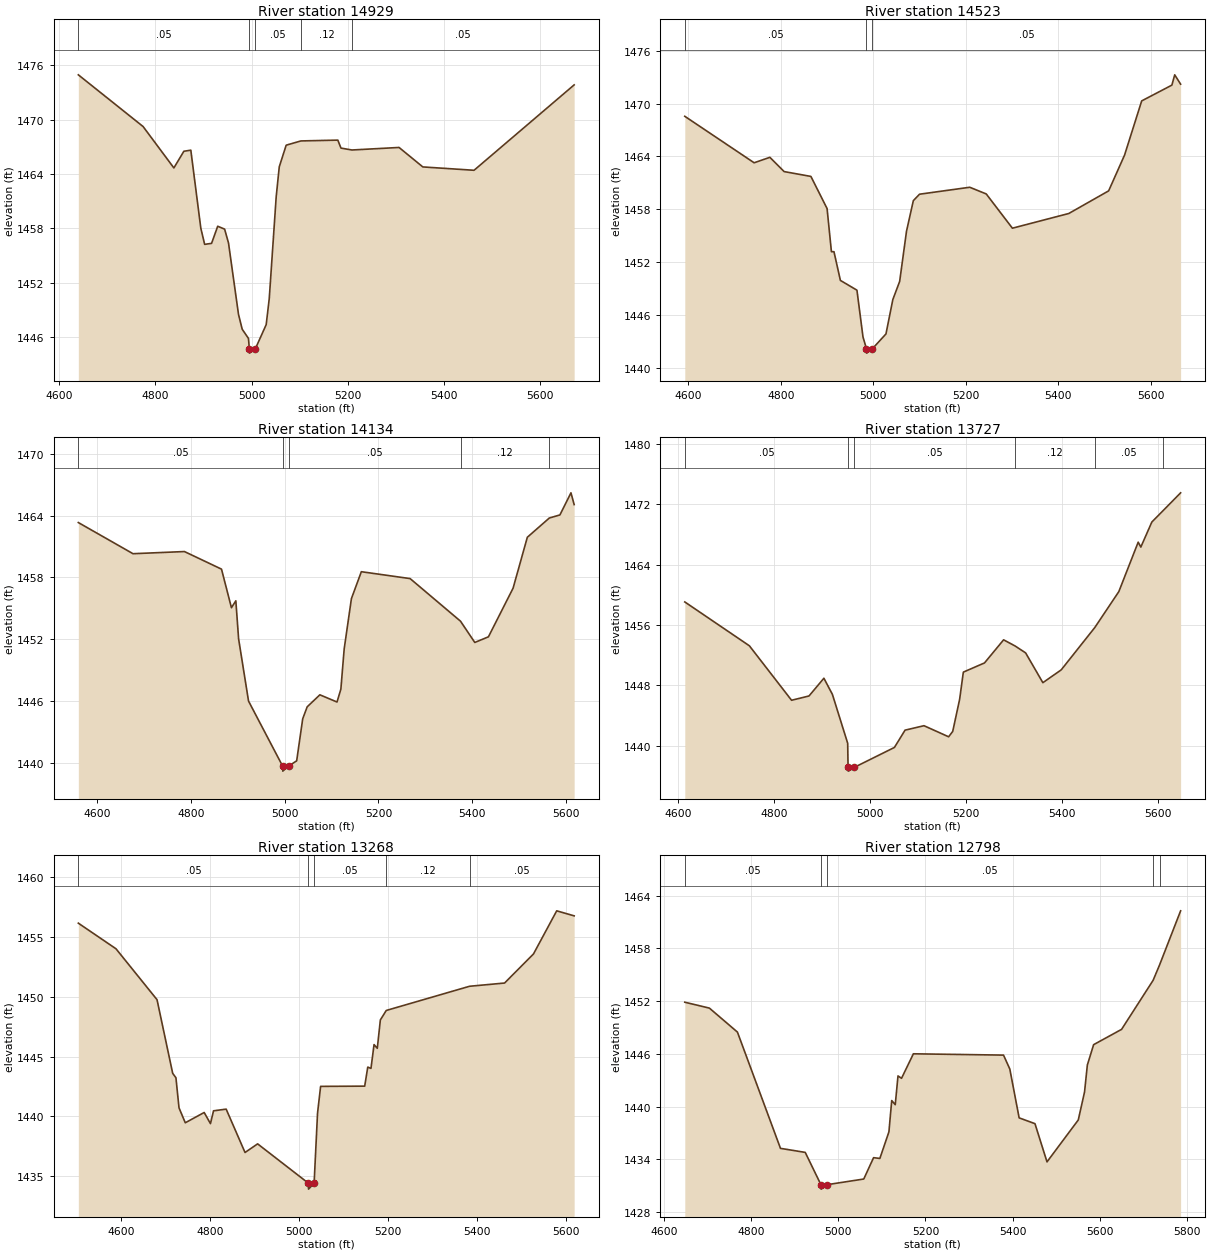
Type RM Length L Ch R = 1 ,14929   ,406,406,406
BEGIN DESCRIPTION:
WALNUT SPRING CREEK 32.0
END DESCRIPTION:
XS GIS Cut Line= 3
      2770228.25     10154654.58      2770631.03     10154335.13
      2770963.39       10153937.
#Sta/Elev= 30
  4639.3 1474.94  4774.2 1469.23  4838.3 1464.66  4859.1  1466.5  4873.6 1466.62
  4894.4 1458.01  4902.4 1456.22  4916.8 1456.33  4929.6 1458.22    4944  1457.9
  4952.1 1456.37  4972.9 1448.49  4980.6 1446.85  4993.7 1445.83  4995.4 1444.71
  4995.9 1444.21  5008.2 1444.71  5030.6 1447.36    5037 1450.26  5051.4 1461.47
  5057.8 1464.78  5072.2 1467.17  5102.8 1467.64  5179.8 1467.73  5186.3 1466.85
  5209.1 1466.64  5307.3 1466.92  5356.8 1464.77  5463.5  1464.4    5672 1473.83
#Mann= 5 ,-1 , 0
  4639.3     .05       0  4995.4     .03       0  5008.2     .05       0
  5102.8     .12       0  5209.1     .05       0
Bank Sta=4995.4,5008.2
XS Rating Curve= 0 ,0
Exp/Cntr=0.3,0.1

Type RM Length L Ch R = 1 ,14523   ,389,389,389
BEGIN DESCRIPTION:
WALNUT SPRING CREEK 31.0
END DESCRIPTION:
XS GIS Cut Line= 3
      2770457.38     10154845.56      2770767.45     10154766.78
      2771200.46     10154151.13
#Sta/Elev= 30
    4592 1468.56    4742 1463.28    4776  1463.9  4806.9 1462.28  4864.8 1461.73
  4899.8 1458.08  4909.2 1453.18  4914.7 1453.18  4928.6 1449.92  4964.4 1448.81
  4977.5 1443.49    4985 1442.16  4985.5 1441.66  4997.9 1442.16  5027.2 1443.84
    5042 1447.74  5056.8  1449.8  5071.6  1455.5  5086.4 1458.98  5099.8 1459.71
  5208.4  1460.5  5244.1 1459.74  5300.7 1455.85  5422.7 1457.52  5508.9 1460.09
  5543.3 1464.15  5580.4 1470.31  5645.7  1472.1  5651.8 1473.27  5664.6 1472.21
#Mann= 3 ,-1 , 0
    4592     .05       0    4985     .03       0  4997.9     .05       0
Bank Sta=4985,4997.9
XS Rating Curve= 0 ,0
Exp/Cntr=0.3,0.1

Type RM Length L Ch R = 1 ,14134   ,407,407,407
BEGIN DESCRIPTION:
WALNUT SPRING CREEK 30.0
END DESCRIPTION:
XS GIS Cut Line= 3
      2770929.64     10155248.34      2771269.92     10154703.18
      2771433.12     10154321.23
#Sta/Elev= 30
  4559.6 1463.34  4676.3 1460.31    4786 1460.52  4865.1 1458.81  4886.3 1455.06
  4895.7 1455.73  4901.6 1452.03  4922.8 1445.98  4995.4 1439.67  4995.9 1439.17
  5008.4 1439.67  5025.5 1440.17  5038.4 1444.26  5047.9 1445.42    5075 1446.59
  5111.6 1445.89  5119.8 1447.14  5126.9 1451.06  5142.3 1455.94  5163.5 1458.56
  5267.6 1457.89  5375.1 1453.75  5405.6 1451.68  5434.7 1452.23  5487.3 1456.96
  5517.7 1461.91  5564.6 1463.78  5587.2 1464.08  5610.8 1466.23  5617.6 1465.09
#Mann= 5 ,-1 , 0
  4559.6     .05       0  4995.4     .05       0  5008.4     .05       0
  5375.1     .12       0  5564.6     .05       0
Bank Sta=4995.4,5008.4
XS Rating Curve= 0 ,0
Exp/Cntr=0.3,0.1

Type RM Length L Ch R = 1 ,13727   ,459,459,459
BEGIN DESCRIPTION:
WALNUT SPRING CREEK 29.0
END DESCRIPTION:
XS GIS Cut Line= 3
      2771405.69     10155403.08        2771533.       10155039.
      2771805.67     10154453.14
#Sta/Elev= 30
  4614.3 1459.04  4748.7 1453.23  4836.5 1446.01  4872.8 1446.58  4903.8 1448.93
  4921.5 1446.79  4953.3 1440.31  4954.1 1437.12  4954.6 1436.62  4967.1 1437.12
  5050.6 1439.76  5072.7 1442.05  5112.1 1442.64  5163.4 1441.17  5171.9 1441.88
  5186.3 1446.14    5194 1449.74  5238.1 1450.96  5277.8 1454.02  5301.8  1453.2
  5323.6 1452.29  5359.5 1448.34  5397.7 1450.04  5467.6 1455.65  5517.6 1460.41
  5557.9 1466.96  5563.4 1466.31  5586.3 1469.63  5609.9 1471.15  5646.2  1473.5
#Mann= 6 ,-1 , 0
  4614.3     .05       0  4954.1     .05       0  4967.1     .05       0
  5301.8     .12       0  5467.6     .05       0  5609.9     .12       0
Bank Sta=4954.1,4967.1
XS Rating Curve= 0 ,0
Exp/Cntr=0.3,0.1

Type RM Length L Ch R = 1 ,13268   ,470,470,470
BEGIN DESCRIPTION:
WALNUT SPRING CREEK 28.0
END DESCRIPTION:
XS GIS Cut Line= 3
      2771605.71     10155503.08      2772103.26     10155029.57
       2772023.4     10154609.45
#Sta/Elev= 30
  4504.6 1456.14  4589.3    1454  4681.5 1449.75  4716.7  1443.6    4724 1443.23
  4730.9 1440.72    4745 1439.47  4787.5 1440.33  4801.6  1439.4  4808.5 1440.47
  4836.9 1440.61  4879.3 1436.99  4907.6 1437.71  5021.6 1434.43  5022.1 1433.93
  5034.6 1434.43  5042.3 1440.28  5049.2 1442.51  5148.3 1442.53  5155.2 1444.12
  5162.4 1444.01  5169.3    1446  5176.6 1445.69  5183.5 1448.06  5196.8 1448.85
    5384 1450.87  5462.7 1451.14  5527.7 1453.57  5579.9 1457.17  5619.1 1456.75
#Mann= 5 ,-1 , 0
  4504.6     .05       0  5021.6     .05       0  5034.6     .05       0
  5196.8     .12       0    5384     .05       0
Bank Sta=5021.6,5034.6
XS Rating Curve= 0 ,0
Exp/Cntr=0.3,0.1

Type RM Length L Ch R = 1 ,12798   ,556,556,556
BEGIN DESCRIPTION:
WALNUT SPRING CREEK 27.0
END DESCRIPTION:
XS GIS Cut Line= 3
      2772005.68     10155753.12       2772267.5       10155518.
      2772755.67     10154903.13
#Sta/Elev= 30
  4648.1 1451.87  4704.5  1451.2  4768.8 1448.47  4867.5 1435.24  4924.3 1434.78
  4960.3  1431.1  4960.8  1430.6  4973.5  1431.1  5058.5 1431.75    5081 1434.18
  5095.4 1434.09  5116.2 1437.12  5122.6 1440.68  5130.7 1440.21    5137 1443.48
  5145.1 1443.21  5172.3    1446    5379 1445.85  5393.4 1444.27  5414.8 1438.71
  5451.1 1438.05  5478.7  1433.7  5550.4 1438.47  5564.8 1441.66  5571.2 1444.72
  5585.6 1447.04  5649.7 1448.78    5722 1454.36  5736.9 1456.12  5785.1 1462.27
#Mann= 5 ,-1 , 0
  4648.1     .05       0  4960.3     .03       0  4973.5     .05       0
    5722     .12       0  5736.9     .05       0
Bank Sta=4960.3,4973.5
XS Rating Curve= 0 ,0
Exp/Cntr=0.3,0.1

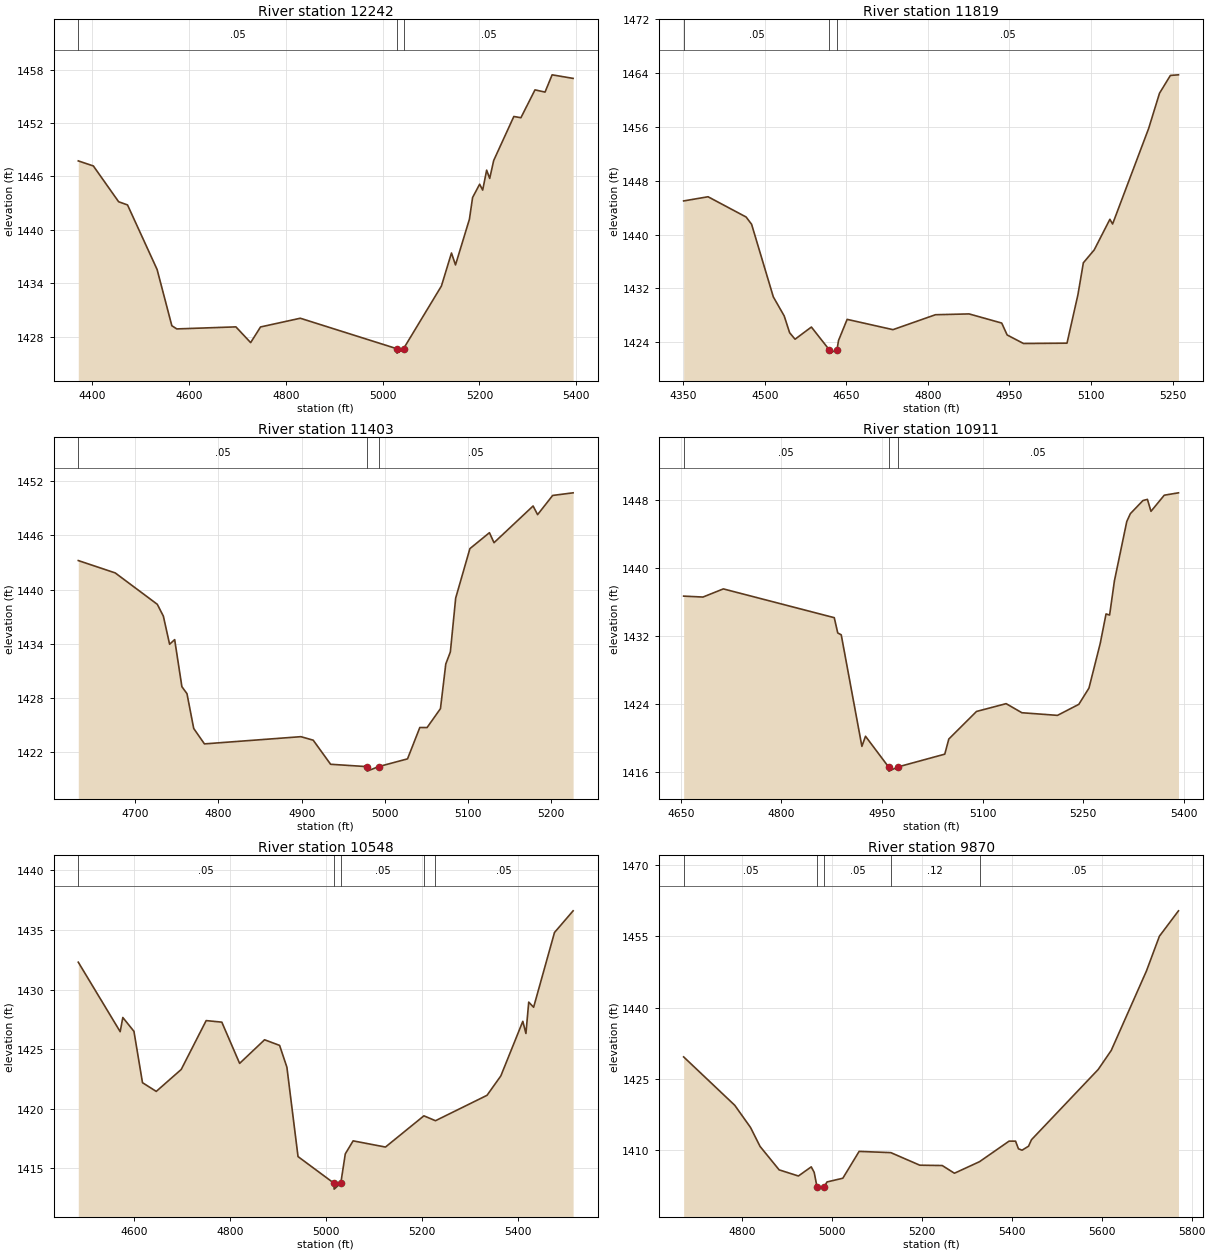
Type RM Length L Ch R = 1 ,12242   ,423,423,423
BEGIN DESCRIPTION:
WALNUT SPRING CREEK 26.0
END DESCRIPTION:
XS GIS Cut Line= 3
      2772205.65     10155953.12      2772679.65     10155862.91
      2773006.04     10155432.34
#Sta/Elev= 30
  4370.9 1447.74  4402.1 1447.17  4454.3 1443.15  4472.7 1442.79  4533.8 1435.54
  4564.3 1429.22  4574.5 1428.86  4696.7 1429.09  4727.2 1427.32  4747.6 1429.08
  4829.8 1430.06  5029.1 1426.64  5029.6 1426.14  5043.2 1426.64  5121.5 1433.68
  5142.3 1437.39  5150.6 1436.05  5179.4 1441.19  5185.9 1443.62  5200.5 1445.12
  5206.8 1444.46    5215  1446.7  5221.3 1445.77  5229.6 1447.79  5271.2 1452.73
  5285.8 1452.59  5314.9 1455.72  5335.7 1455.47  5350.3 1457.41  5393.7 1457.01
#Mann= 3 ,-1 , 0
  4370.9     .05       0  5029.1     .03       0  5043.2     .05       0
Bank Sta=5029.1,5043.2
XS Rating Curve= 0 ,0
Exp/Cntr=0.3,0.1

Type RM Length L Ch R = 1 ,11819   ,416,416,416
BEGIN DESCRIPTION:
WALNUT SPRING CREEK 25.0
END DESCRIPTION:
XS GIS Cut Line= 3
      2772290.78     10156109.44      2772757.19     10156122.86
      2773200.52     10156102.49
#Sta/Elev= 30
  4350.5 1445.01  4395.4 1445.63  4465.4 1442.62  4475.5 1441.54  4515.5 1430.74
  4535.5 1427.91  4545.5 1425.41  4555.5 1424.45  4585.5 1426.26  4618.4 1422.88
  4618.9 1422.38  4632.6 1422.88  4635.5 1424.27  4651.3  1427.4  4735.6 1425.87
  4813.8 1428.09  4875.7 1428.21  4935.7 1426.85  4945.7 1425.08  4975.8 1423.81
  5055.8 1423.86  5075.9 1431.06  5085.9 1435.81  5105.9 1437.73  5134.7 1442.28
  5139.7 1441.58    5206 1455.78    5226 1461.02    5246 1463.67  5260.9 1463.76
#Mann= 3 ,-1 , 0
  4350.5     .05       0  4618.4     .03       0  4632.6     .05       0
Bank Sta=4618.4,4632.6
XS Rating Curve= 0 ,0
Exp/Cntr=0.3,0.1

Type RM Length L Ch R = 1 ,11403   ,492,492,492
BEGIN DESCRIPTION:
WALNUT SPRING CREEK 24.0
END DESCRIPTION:
XS GIS Cut Line= 3
      2772401.85     10156234.42      2772758.91      10156483.8
      2772905.35     10156546.94
#Sta/Elev= 30
  4631.4 1443.22  4675.8 1441.85  4726.4 1438.37  4733.7 1437.06  4741.2 1433.94
  4747.3 1434.45    4756 1429.23  4762.1 1428.46  4770.2  1424.6  4783.1 1422.89
  4899.1 1423.69  4913.9  1423.3  4934.8 1420.63  4978.3 1420.37  4978.8 1419.87
  4992.5 1420.37  5027.3 1421.23  5042.1 1424.71  5050.8  1424.7  5066.9  1426.8
  5073.3 1431.75  5078.8 1433.08  5085.2 1439.06  5102.3 1444.54  5125.8 1446.31
  5131.3  1445.2  5178.3 1449.27  5183.7 1448.31  5201.8 1450.44  5226.4 1450.73
#Mann= 3 ,-1 , 0
  4631.4     .05       0  4978.3     .03       0  4992.5     .05       0
Bank Sta=4978.3,4992.5
XS Rating Curve= 0 ,0
Exp/Cntr=0.3,0.1

Type RM Length L Ch R = 1 ,10911   ,363,363,363
BEGIN DESCRIPTION:
WALNUT SPRING CREEK 23.0
END DESCRIPTION:
XS GIS Cut Line= 3
      2772047.69     10156692.76      2772481.73     10156800.41
      2772755.67     10156703.12
#Sta/Elev= 30
  4654.3 1436.73  4683.1 1436.62  4713.5 1437.58  4878.9 1434.19  4884.1 1432.39
  4889.3 1432.17  4920.1 1419.03  4925.5 1420.22  4959.8 1416.61  4960.3 1416.11
  4974.1 1416.61  5043.7 1418.11  5049.7 1419.89    5091 1423.14  5135.2 1424.06
  5158.7 1422.99  5211.8 1422.68  5243.6 1423.98  5258.7 1425.89  5275.5 1431.15
  5284.2 1434.63  5289.5  1434.5  5296.7 1438.54  5315.1 1445.52  5320.4 1446.44
  5339.2 1447.99  5345.9 1448.13  5351.2 1446.72    5371 1448.62  5392.2  1448.9
#Mann= 3 ,-1 , 0
  4654.3     .05       0  4959.8     .03       0  4974.1     .05       0
Bank Sta=4959.8,4974.1
XS Rating Curve= 0 ,0
Exp/Cntr=0.3,0.1

Type RM Length L Ch R = 1 ,10548   ,678,678,678
BEGIN DESCRIPTION:
WALNUT SPRING CREEK 22.0
END DESCRIPTION:
XS GIS Cut Line= 3
      2771862.38     10157344.21      2772411.19     10157100.21
      2772787.26      10156890.7
#Sta/Elev= 30
    4483  1432.3  4570.3 1426.47  4575.8 1427.66    4599  1426.5  4616.8 1422.19
  4645.5 1421.46  4697.5  1423.3  4749.5  1427.4  4782.1 1427.27  4819.2 1423.81
  4871.2 1425.79  4902.5 1425.32  4917.7 1423.49  4940.9 1415.99  5015.7 1413.76
  5016.2 1413.26    5030 1413.76  5039.4 1416.22  5055.7 1417.31  5123.1 1416.79
  5203.2 1419.41  5227.3    1419  5334.7 1421.13  5363.5 1422.76  5409.3 1427.34
  5415.8 1426.32  5421.6 1428.95  5431.8 1428.52  5475.3 1434.79  5514.1 1436.61
#Mann= 5 ,-1 , 0
    4483     .05       0  5015.7     .05       0    5030     .05       0
  5203.2     .12       0  5227.3     .05       0
Bank Sta=5015.7,5030
XS Rating Curve= 0 ,0
Exp/Cntr=0.3,0.1

Type RM Length L Ch R = 1 ,9870    ,485,485,485
BEGIN DESCRIPTION:
WALNUT SPRING CREEK 21.0
END DESCRIPTION:
XS GIS Cut Line= 3
      2772405.69      10157903.1      2772745.62     10157616.38
      2773155.71     10157103.08
#Sta/Elev= 30
    4669 1429.67  4782.8  1419.5  4817.9 1414.84  4839.1 1410.86  4881.6 1405.93
  4924.5 1404.64  4953.1 1406.56  4959.6 1405.41  4965.9 1402.38  4966.4 1401.88
  4981.9 1402.38  4988.2 1403.39  5023.4 1404.17  5059.7 1409.81  5130.3 1409.55
  5194.7 1406.91  5244.7 1406.84  5271.9 1405.22  5327.8 1407.65  5393.6 1411.97
    5408 1411.96  5414.4 1410.36  5422.4 1410.06  5436.9  1410.9  5443.3 1412.25
  5592.1 1427.04    5621 1431.03  5699.4 1447.73  5728.2 1455.03  5770.7 1460.37
#Mann= 5 ,-1 , 0
    4669     .05       0  4965.9     .05       0  4981.9     .05       0
  5130.3     .12       0  5327.8     .05       0
Bank Sta=4965.9,4981.9
XS Rating Curve= 0 ,0
Exp/Cntr=0.3,0.1

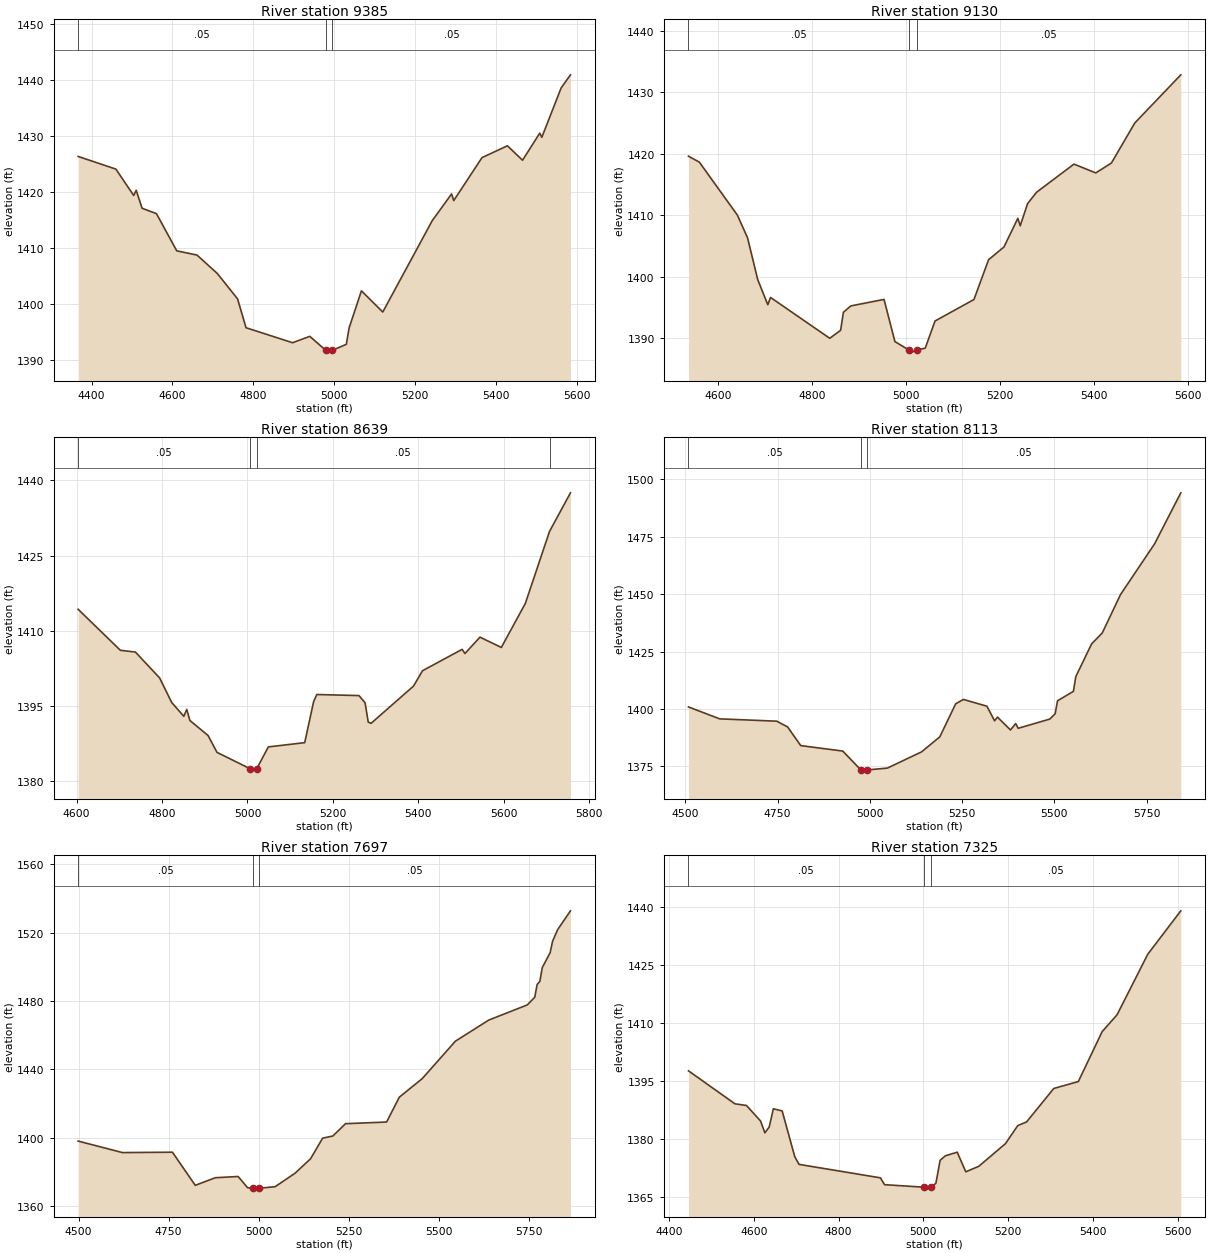
Type RM Length L Ch R = 1 ,9385    ,255,255,255
BEGIN DESCRIPTION:
WALNUT SPRING CREEK 20.0
END DESCRIPTION:
XS GIS Cut Line= 3
      2772766.46      10158324.7      2773016.45     10157984.43
        2773197.     10157210.14
#Sta/Elev= 30
  4366.8 1426.31  4460.1 1424.04  4504.1 1419.33  4510.3 1420.26  4524.9 1417.04
  4560.4 1416.08  4610.6 1409.43  4660.7 1408.67  4710.9 1405.38    4761 1400.83
  4781.9 1395.68    4897    1393  4939.5 1394.14  4979.2 1391.64  4979.7 1391.14
  4995.2 1391.64  5029.8 1392.71  5036.8 1395.65  5067.2 1402.28    5120 1398.49
  5242.2 1414.81  5290.2 1419.61  5295.4 1418.41  5365.4  1426.1  5428.2 1428.21
  5465.6 1425.63  5508.1 1430.47  5513.3 1429.73    5561 1438.55  5584.1  1440.9
#Mann= 3 ,-1 , 0
  4366.8     .05       0  4979.2     .05       0  4995.2     .05       0
Bank Sta=4979.2,4995.2
XS Rating Curve= 0 ,0
Exp/Cntr=0.3,0.1

Type RM Length L Ch R = 1 ,9130    ,491,491,491
BEGIN DESCRIPTION:
WALNUT SPRING CREEK 19.0
END DESCRIPTION:
XS GIS Cut Line= 3
      2773055.67     10158303.14        2773287.       10157903.
      2773440.07     10157338.59
#Sta/Elev= 30
  4537.8  1419.6  4560.9 1418.63  4641.8    1410  4663.4 1406.31    4685 1399.51
  4706.5  1395.4  4712.3 1396.59  4838.2 1389.94  4861.3 1391.23  4867.3 1394.17
    4883 1395.21  4953.7 1396.27  4976.8  1389.4  5006.7 1388.02  5007.2 1387.52
  5022.8 1388.02  5041.3 1388.33  5062.1 1392.75  5144.9 1396.25    5176 1402.73
  5208.7 1404.81  5238.2 1409.47  5243.3 1408.26  5258.9 1411.86    5278 1413.72
  5357.6 1418.31    5404 1416.87  5437.3 1418.49  5486.9    1425  5584.8 1432.85
#Mann= 3 ,-1 , 0
  4537.8     .05       0  5006.7     .05       0  5022.8     .05       0
Bank Sta=5006.7,5022.8
XS Rating Curve= 0 ,0
Exp/Cntr=0.3,0.1

Type RM Length L Ch R = 1 ,8639    ,526,526,526
BEGIN DESCRIPTION:
WALNUT SPRING CREEK 18.0
END DESCRIPTION:
XS GIS Cut Line= 3
      2773280.31     10158557.38      2773571.25       10158288.
      2774134.53     10157783.02
#Sta/Elev= 30
  4603.5 1414.29  4702.4 1406.11  4737.6 1405.76  4794.3  1400.6  4822.6 1395.69
    4851 1392.95  4857.8 1394.32  4865.2 1392.11  4907.7 1389.12  4928.7 1385.75
  5005.7 1382.51  5006.2 1382.01  5021.8 1382.51  5048.9 1386.84  5134.1 1387.69
    5155 1395.89  5162.5 1397.29  5261.2 1397.08  5275.4 1395.66  5282.9 1391.78
  5289.6 1391.55    5389 1398.98  5409.9 1402.03  5502.7  1406.3  5509.4 1405.47
  5544.5 1408.73  5594.6 1406.68  5650.7 1415.44  5707.5 1429.83  5756.5 1437.52
#Mann= 4 ,-1 , 0
  4603.5     .05       0  5005.7     .05       0  5021.8     .05       0
  5707.5     .12       0
Bank Sta=5005.7,5021.8
XS Rating Curve= 0 ,0
Exp/Cntr=0.3,0.1

Type RM Length L Ch R = 1 ,8113    ,416,416,416
BEGIN DESCRIPTION:
WALNUT SPRING CREEK 17.0
END DESCRIPTION:
XS GIS Cut Line= 3
      2773544.22     10158730.97      2773899.46     10158585.17
       2774505.7      10157853.1
#Sta/Elev= 30
  4508.4  1400.9    4593 1395.71  4747.7  1394.7  4777.1 1392.19  4812.7 1384.06
  4926.6 1381.68  4975.8 1373.44  4976.3 1372.94    4992 1373.44  5047.7 1374.27
  5140.2 1381.33  5189.7 1387.88  5232.6 1402.25  5253.5 1404.17  5317.3 1401.23
  5338.2 1394.86    5346 1396.46  5381.2 1390.87  5395.5 1393.67    5402 1391.59
    5488 1395.63  5502.3 1397.95  5508.8 1403.59  5551.8 1407.69  5558.3 1414.11
  5601.3 1428.41  5629.9 1433.09  5679.4 1449.83  5771.9 1471.97  5842.9 1494.18
#Mann= 3 ,-1 , 0
  4508.4     .05       0  4975.8     .03       0    4992     .05       0
Bank Sta=4975.8,4992
XS Rating Curve= 0 ,0
Exp/Cntr=0.3,0.1

Type RM Length L Ch R = 1 ,7697    ,372,372,372
BEGIN DESCRIPTION:
WALNUT SPRING CREEK 16.0
END DESCRIPTION:
XS GIS Cut Line= 3
      2773717.83     10158998.33      2774328.95     10158793.46
      2774805.66     10158253.14
#Sta/Elev= 30
    4499 1398.03  4621.8 1391.29  4760.4 1391.51  4823.7 1372.12  4879.5 1376.57
  4942.6  1377.3  4968.8 1370.72  4984.2  1370.4  4984.7  1369.9  5000.6  1370.4
  5045.2 1371.33  5100.3 1379.19  5143.5 1387.69  5176.9 1399.73  5205.3    1401
  5240.4 1408.21  5354.3 1409.17  5389.4 1423.69  5452.9 1434.56    5545  1456.5
  5637.4 1468.83  5744.1 1477.71    5765 1482.18  5771.7 1489.71  5779.2 1491.48
  5785.9 1499.56  5807.7 1508.31  5814.4 1514.94  5828.6 1521.81  5864.1  1532.8
#Mann= 3 ,-1 , 0
    4499     .05       0  4984.2     .05       0  5000.6     .05       0
Bank Sta=4984.2,5000.6
XS Rating Curve= 0 ,0
Exp/Cntr=0.3,0.1

Type RM Length L Ch R = 1 ,7325    ,488,488,488
BEGIN DESCRIPTION:
WALNUT SPRING CREEK 15.0
END DESCRIPTION:
XS GIS Cut Line= 3
      2773697.03      10159276.1      2774392.67     10159185.35
      2774755.72     10158903.09
#Sta/Elev= 30
  4445.9 1397.65  4555.5 1389.14  4582.8  1388.7    4616 1384.69  4626.1 1381.64
  4636.2 1383.12  4646.2 1387.86  4666.9  1387.3  4696.7 1375.47  4706.7 1373.51
  4898.8 1370.03  4908.4 1368.27    5001 1367.62  5001.5 1367.12  5017.5 1367.62
  5029.5  1368.6  5039.5 1374.54  5051.7 1375.71  5079.9 1376.65  5100.1 1371.59
  5130.7 1373.01  5193.7 1378.86  5222.7 1383.52  5243.5 1384.46  5307.7  1393.1
  5365.6 1394.88  5421.7 1407.75    5457 1412.12  5529.4 1427.74  5607.3 1438.94
#Mann= 3 ,-1 , 0
  4445.9     .05       0    5001     .03       0  5017.5     .05       0
Bank Sta=5001,5017.5
XS Rating Curve= 0 ,0
Exp/Cntr=0.3,0.1

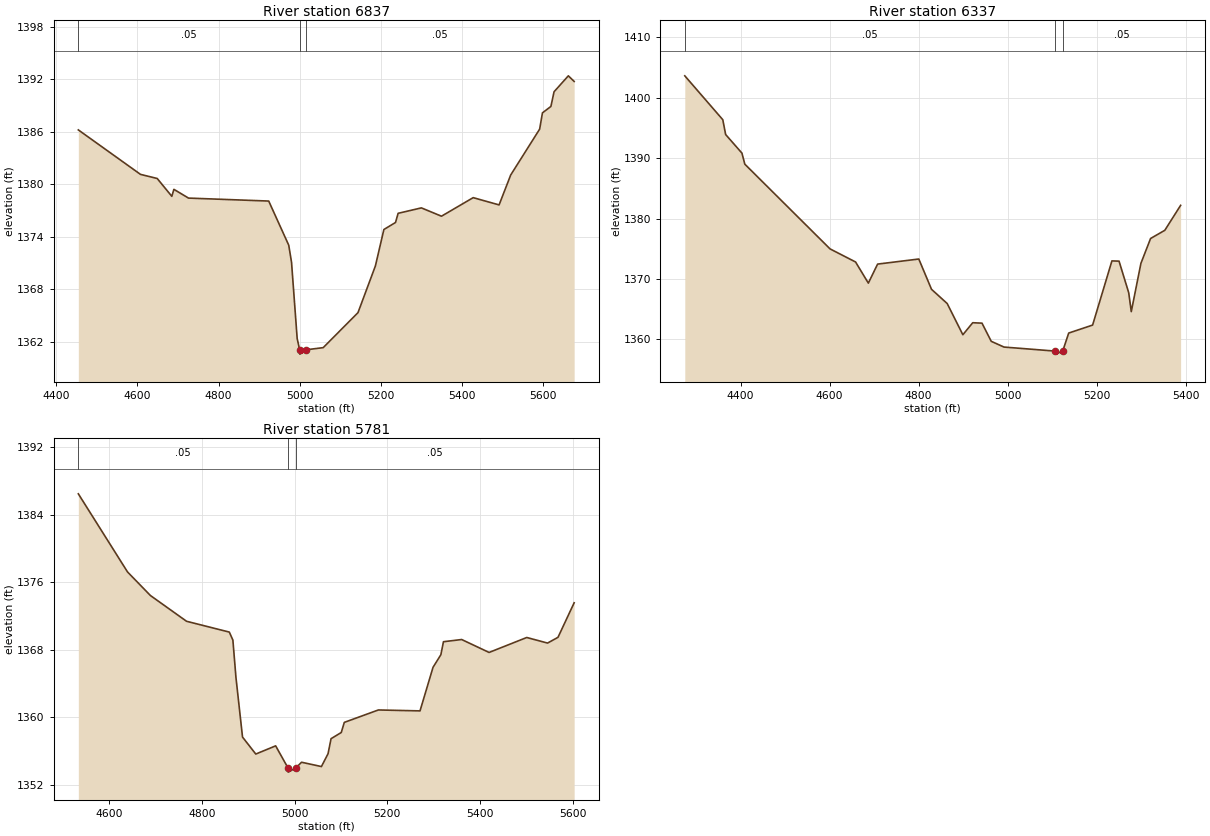
Type RM Length L Ch R = 1 ,6837    ,500,500,500
BEGIN DESCRIPTION:
WALNUT SPRING CREEK 14.0
END DESCRIPTION:
XS GIS Cut Line= 3
      2773887.99     10159814.29      2774340.94     10159700.69
      2774921.08     10159218.42
#Sta/Elev= 30
  4454.6  1386.2  4607.7 1381.12  4648.9 1380.65  4684.9 1378.61    4690 1379.41
    4726 1378.41  4923.6 1378.07  4972.9 1373.03  4979.8 1371.08  4993.7 1362.36
  4999.8 1361.08  5000.3 1360.58  5016.4 1361.08  5057.8 1361.32  5143.5 1365.32
  5186.4 1370.66  5207.3 1374.82  5235.9 1375.62  5242.4 1376.67  5299.7 1377.29
  5349.2 1376.34  5427.3 1378.46  5491.1 1377.63  5519.7 1381.05    5591 1386.29
  5597.9 1388.15  5618.7 1388.88  5626.5 1390.56  5661.7 1392.38    5676 1391.74
#Mann= 3 ,-1 , 0
  4454.6     .05       0  4999.8     .03       0  5016.4     .05       0
Bank Sta=4999.8,5016.4
XS Rating Curve= 0 ,0
Exp/Cntr=0.3,0.1

Type RM Length L Ch R = 1 ,6337    ,556,556,556
BEGIN DESCRIPTION:
WALNUT SPRING CREEK 13.0
END DESCRIPTION:
XS GIS Cut Line= 3
      2774305.69      10160503.1       2774766.5       10159943.
      2774955.69      10159603.1
#Sta/Elev= 30
  4274.7 1403.65  4360.1 1396.38  4366.5 1393.93  4403.1 1390.85  4409.6 1389.02
  4601.1 1374.99  4658.5 1372.82  4687.2 1369.32    4708 1372.47  4800.6 1373.31
  4829.2 1368.29  4864.4 1365.94  4899.6 1360.77  4921.8 1362.76  4942.6 1362.69
  4963.4 1359.68  4992.1 1358.73  5107.4 1358.06  5107.9 1357.56    5124 1358.06
  5137.5 1361.05  5191.2 1362.37  5234.6    1373  5250.6 1372.96  5272.4 1367.72
  5278.1  1364.6  5299.8  1372.6  5321.5 1376.71  5353.5 1378.07    5389  1382.2
#Mann= 3 ,-1 , 0
  4274.7     .05       0  5107.4     .05       0    5124     .05       0
Bank Sta=5107.4,5124
XS Rating Curve= 0 ,0
Exp/Cntr=0.3,0.1

Type RM Length L Ch R = 1 ,5781    ,254,254,254
BEGIN DESCRIPTION:
WALNUT SPRING CREEK 12.0
END DESCRIPTION:
XS GIS Cut Line= 3
      2774860.24     10160557.32      2775322.01     10160164.99
      2775526.85     10159748.36
#Sta/Elev= 30
    4533 1386.46  4639.2 1377.21  4688.6 1374.42  4766.6 1371.37  4858.9 1370.09
  4866.6 1369.14  4873.2 1364.73  4887.4 1357.66    4916 1355.65  4958.9 1356.62
  4985.5 1354.01    4986 1353.51  5002.5 1354.01  5014.8 1354.68  5057.7 1354.17
    5072 1355.69  5078.5 1357.47  5100.5  1358.2  5107.1  1359.4  5180.6 1360.87
  5270.5 1360.76  5298.6 1365.92  5315.5 1367.41  5321.1 1368.95  5360.4 1369.21
  5419.6 1367.68  5500.9 1369.45  5545.8 1368.79  5568.3 1369.47  5603.2 1373.56
#Mann= 3 ,-1 , 0
    4533     .05       0  4985.5     .03       0  5002.5     .05       0
Bank Sta=4985.5,5002.5
XS Rating Curve= 0 ,0
Exp/Cntr=0.3,0.1