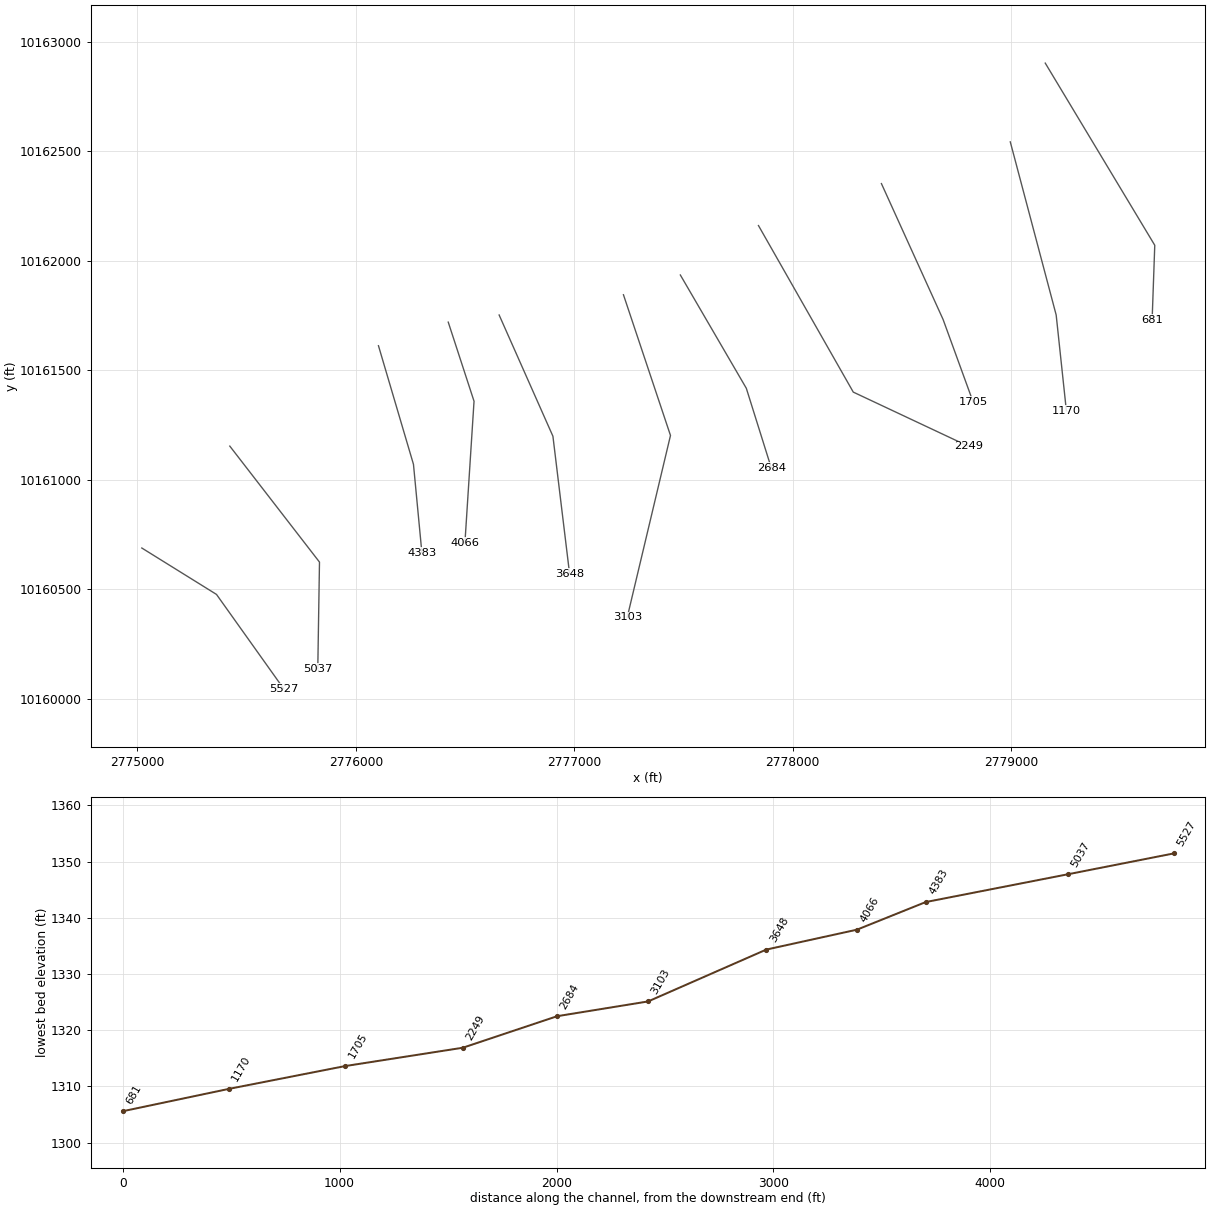
HEC-RAS study WALNUT SPRING CREEK.prj: WALNUT SPRING CREEK Base Level Engineering

--- WALNUT SPRING CREEK.g01 (geometry) --- (continued)

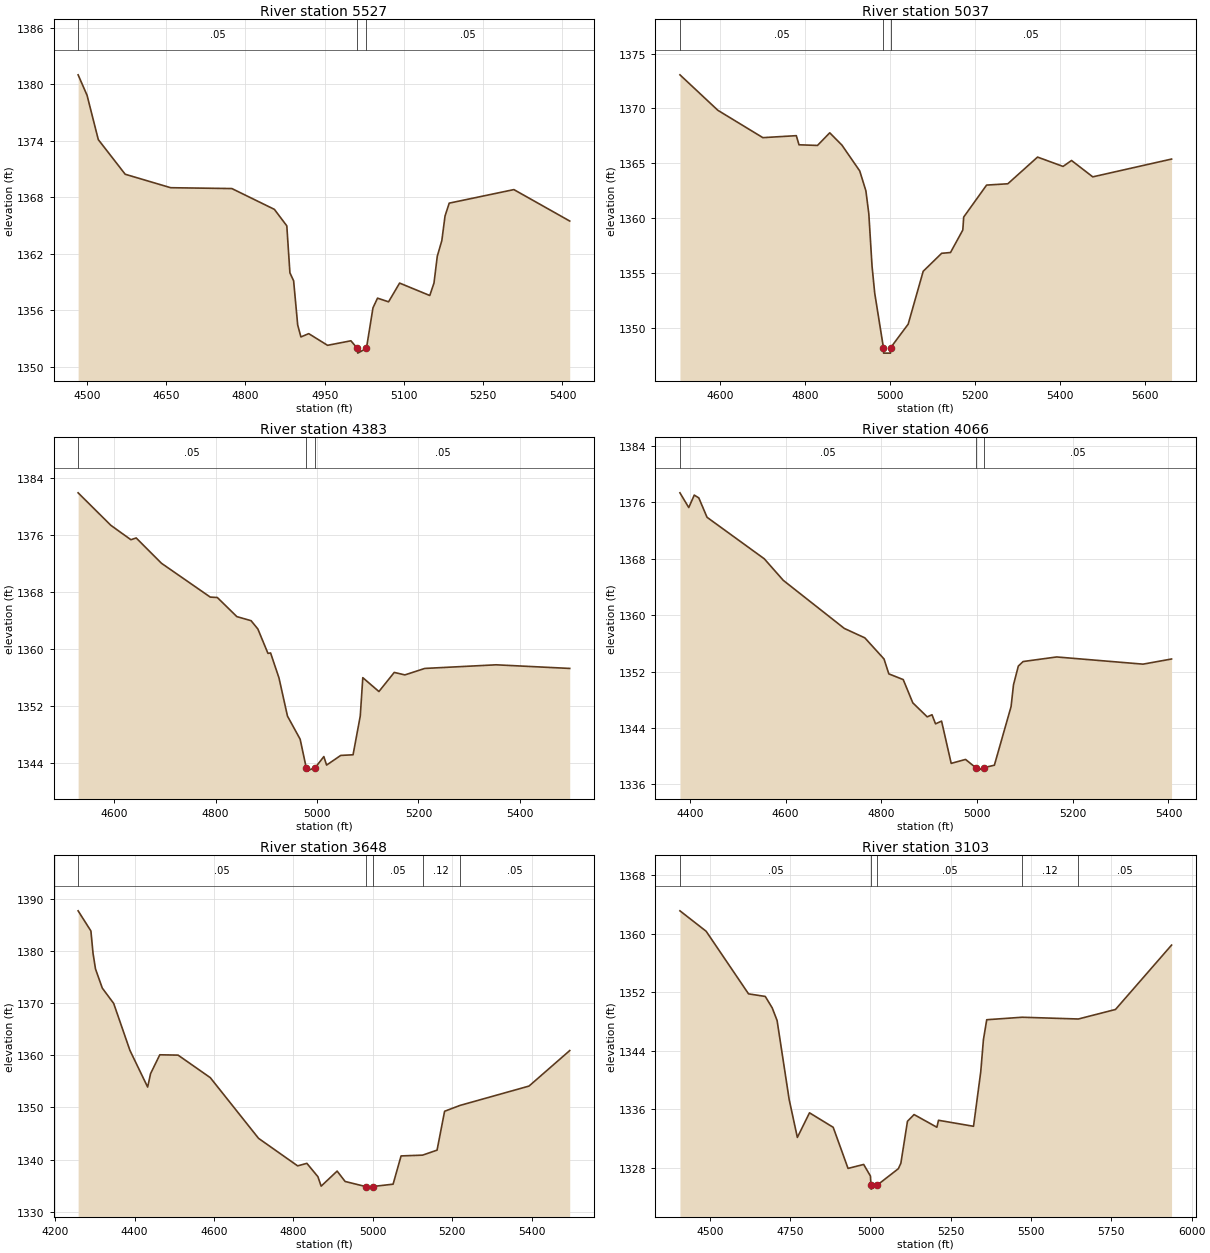
Type RM Length L Ch R = 1 ,5527    ,490,490,490
BEGIN DESCRIPTION:
WALNUT SPRING CREEK 11.0
END DESCRIPTION:
XS GIS Cut Line= 3
      2775019.94     10160689.29       2775361.8     10160477.44
      2775668.83      10160047.5
#Sta/Elev= 30
  4483.3    1381  4500.2 1378.83  4521.5 1374.12  4572.4 1370.44  4658.5 1369.01
  4774.3 1368.92  4854.8 1366.71  4878.3 1364.96  4884.2 1359.97  4891.2 1359.12
  4898.9 1354.43    4905 1353.16  4919.8 1353.51  4955.4 1352.27  4999.6 1352.75
    5012 1351.94  5012.5 1351.44    5029 1351.94  5041.4 1356.25    5050 1357.28
  5070.9 1356.89  5091.8 1358.88  5148.9 1357.56  5156.9 1358.89  5163.1 1361.73
  5171.7 1363.39  5177.8 1366.01  5185.7 1367.37  5308.1 1368.81  5413.8 1365.47
#Mann= 3 ,-1 , 0
  4483.3     .05       0    5012     .03       0    5029     .05       0
Bank Sta=5012,5029
XS Rating Curve= 0 ,0
Exp/Cntr=0.3,0.1

Type RM Length L Ch R = 1 ,5037    ,654,654,654
BEGIN DESCRIPTION:
WALNUT SPRING CREEK 10.0
END DESCRIPTION:
XS GIS Cut Line= 3
      2775422.72     10161154.54      2775833.29     10160625.05
      2775825.49     10160137.63
#Sta/Elev= 30
  4505.7 1373.06    4595 1369.83  4700.9 1367.34  4779.7 1367.52    4786 1366.69
  4829.5 1366.63  4858.4 1367.78  4887.1 1366.66    4929 1364.31  4943.5  1362.5
  4950.4 1360.41    4958 1355.64  4964.3 1353.18  4984.8 1348.22  4985.3 1347.72
  5001.4 1347.72  5001.9 1348.22  5043.1 1350.36  5078.4 1355.17  5121.9 1356.81
  5142.7 1356.88  5171.7 1358.93  5173.8 1360.11  5227.7 1363.02  5277.7 1363.14
  5347.7 1365.57  5407.7 1364.72  5427.7 1365.26  5477.7 1363.77  5663.2 1365.39
#Mann= 3 ,-1 , 0
  4505.7     .05       0  4984.8     .05       0  5001.9     .05       0
Bank Sta=4984.8,5001.9
XS Rating Curve= 0 ,0
Exp/Cntr=0.3,0.1

Type RM Length L Ch R = 1 ,4383    ,317,317,317
BEGIN DESCRIPTION:
WALNUT SPRING CREEK 9.0
END DESCRIPTION:
XS GIS Cut Line= 3
      2776103.26      10161612.9      2776263.52     10161071.29
      2776301.94     10160668.64
#Sta/Elev= 30
    4529 1381.95  4593.5 1377.38  4633.1 1375.35  4643.5  1375.6  4693.3 1372.04
  4789.5 1367.28  4803.5 1367.22    4842 1364.53    4870 1363.96  4883.4 1362.79
  4903.3 1359.36  4908.5 1359.42  4925.1 1355.89  4941.8 1350.53  4966.8 1347.28
  4978.7 1343.29  4979.2 1342.79  4996.6 1343.29  5013.5 1344.84  5018.9 1343.64
  5046.8    1345  5071.1 1345.09  5085.3 1350.55  5090.3 1355.94  5122.1 1353.99
  5152.3 1356.68  5173.3 1356.33  5212.5 1357.24  5353.2 1357.75  5498.3 1357.24
#Mann= 3 ,-1 , 0
    4529     .05       0  4978.7     .03       0  4996.6     .05       0
Bank Sta=4978.7,4996.6
XS Rating Curve= 0 ,0
Exp/Cntr=0.3,0.1

Type RM Length L Ch R = 1 ,4066    ,418,418,418
BEGIN DESCRIPTION:
WALNUT SPRING CREEK 8.0
END DESCRIPTION:
XS GIS Cut Line= 3
      2776422.69     10161720.58      2776540.76     10161359.43
      2776499.09     10160713.63
#Sta/Elev= 30
  4379.4 1377.37  4397.8 1375.28  4409.3 1377.05  4418.8 1376.65    4436  1373.9
  4555.6 1368.01  4595.3 1364.95  4722.8 1358.13  4765.7 1356.79  4805.8 1353.79
  4815.8 1351.68  4845.9 1350.87  4865.9 1347.57    4896 1345.58    4906 1345.88
  4913.4 1344.59    4926 1344.98  4946.1 1338.98  4976.1 1339.54  4997.2 1338.38
  4997.7 1337.88  5015.2 1338.38  5036.3 1338.72  5071.2 1347.03  5076.3 1350.14
  5086.4 1352.79  5096.4 1353.43  5166.5 1354.08  5346.9 1353.06  5406.5 1353.79
#Mann= 3 ,-1 , 0
  4379.4     .05       0  4997.2     .03       0  5015.2     .05       0
Bank Sta=4997.2,5015.2
XS Rating Curve= 0 ,0
Exp/Cntr=0.3,0.1

Type RM Length L Ch R = 1 ,3648    ,545,545,545
BEGIN DESCRIPTION:
WALNUT SPRING CREEK 7.0
END DESCRIPTION:
XS GIS Cut Line= 3
      2776655.67     10161753.15      2776901.87     10161199.71
      2776978.25     10160571.26
#Sta/Elev= 30
  4257.5 1387.73  4289.7 1383.87  4295.1 1379.57  4301.3 1376.58  4318.4 1372.91
  4347.1 1369.97  4388.1 1360.95  4432.7 1353.92  4440.1  1356.5  4463.3 1360.11
  4509.3 1360.05  4590.5 1355.73  4712.2 1344.08  4810.7  1338.8  4833.9 1339.29
  4861.8 1336.72  4869.9 1334.91  4910.2  1337.8  4930.3 1335.81  4981.7 1334.84
  4982.2 1334.34  4999.8 1334.84  5051.2 1335.29  5071.3 1340.71  5125.5 1340.86
    5162 1341.82    5181 1349.28  5219.9  1350.4  5393.7 1354.11  5496.3 1360.92
#Mann= 5 ,-1 , 0
  4257.5     .05       0  4981.7     .05       0  4999.8     .05       0
  5125.5     .12       0  5219.9     .05       0
Bank Sta=4981.7,4999.8
XS Rating Curve= 0 ,0
Exp/Cntr=0.3,0.1

Type RM Length L Ch R = 1 ,3103    ,419,419,419
BEGIN DESCRIPTION:
WALNUT SPRING CREEK 6.0
END DESCRIPTION:
XS GIS Cut Line= 3
      2777224.77     10161845.59      2777440.06     10161203.18
      2777242.14     10160373.29
#Sta/Elev= 30
  4406.7 1363.12  4488.3 1360.33  4620.3 1351.78  4672.4 1351.43  4694.1 1349.86
  4709.2 1348.14  4746.8 1337.35  4772.3 1332.18  4810.1 1335.54  4883.9 1333.56
  4930.1 1327.95  4978.8 1328.49  4999.9  1326.9  5001.4 1325.62  5001.9 1325.12
  5019.5 1325.62  5086.8 1327.91  5094.6 1328.66  5115.1 1334.38  5135.7  1335.3
  5206.7 1333.57  5211.8 1334.52  5320.8  1333.7  5343.3 1341.14  5351.6 1345.52
  5361.9 1348.25  5472.4 1348.59  5647.2 1348.35  5762.8 1349.65  5937.4 1358.44
#Mann= 5 ,-1 , 0
  4406.7     .05       0  5001.4     .05       0  5019.5     .05       0
  5472.4     .12       0  5647.2     .05       0
Bank Sta=5001.4,5019.5
XS Rating Curve= 0 ,0
Exp/Cntr=0.3,0.1

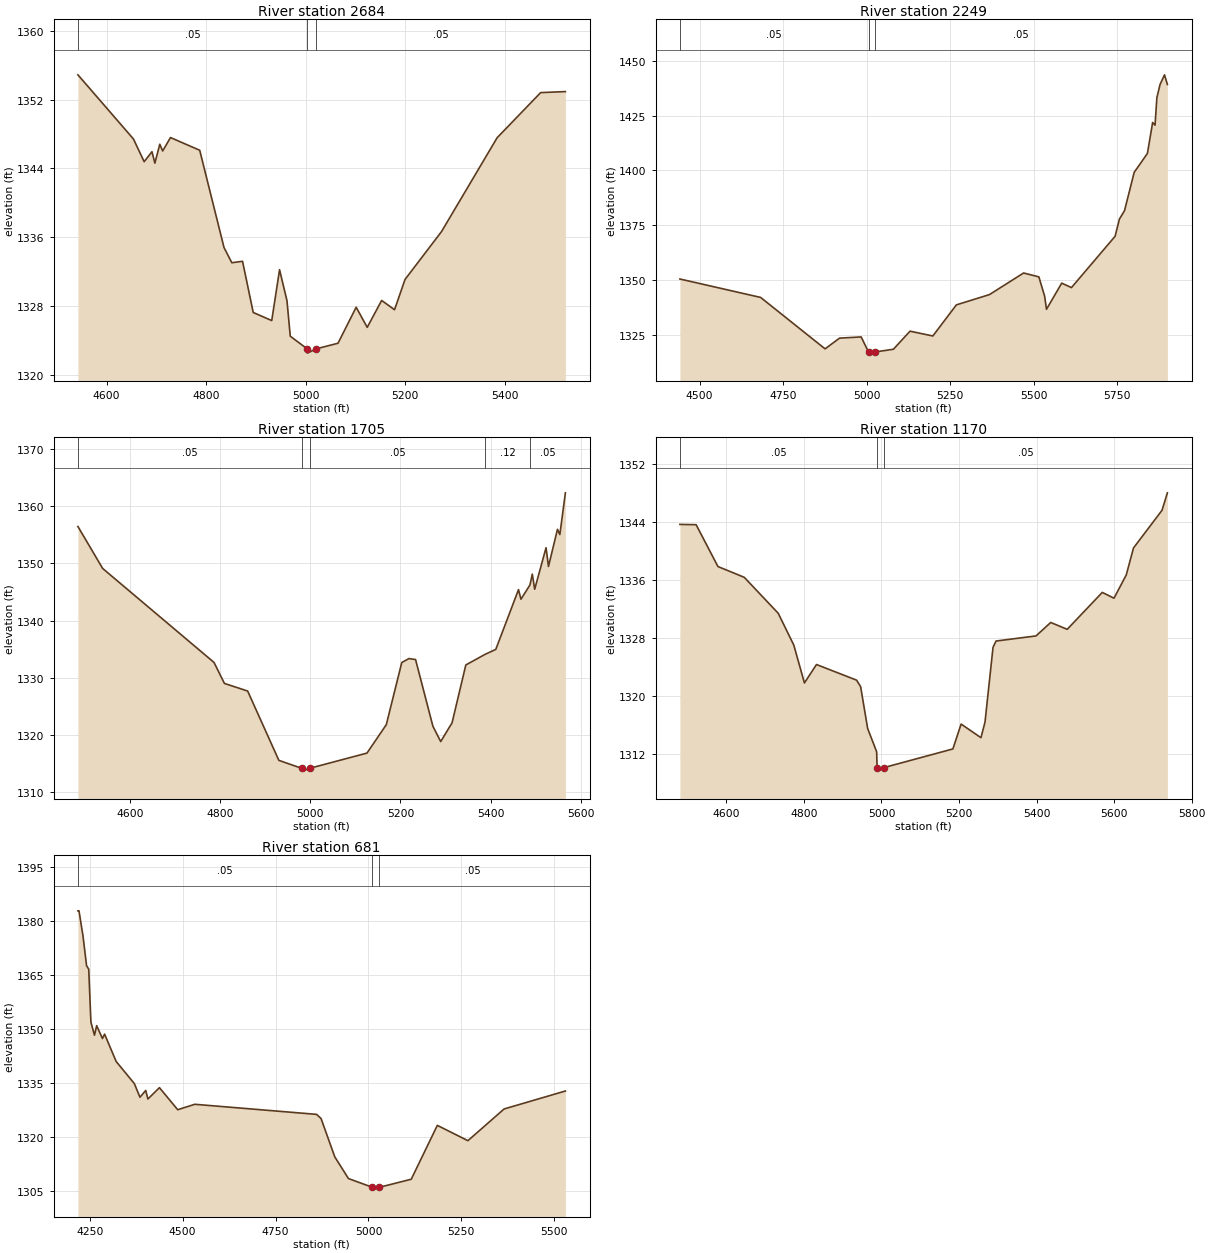
Type RM Length L Ch R = 1 ,2684    ,435,435,435
BEGIN DESCRIPTION:
WALNUT SPRING CREEK 5.0
END DESCRIPTION:
XS GIS Cut Line= 3
      2777485.21     10161935.81      2777787.28     10161418.46
      2777901.28     10161055.74
#Sta/Elev= 30
  4542.3 1354.89  4653.9 1347.42  4675.4 1344.78  4691.1 1345.94  4696.9 1344.61
  4706.8 1346.81  4712.6 1346.03  4728.3 1347.59    4787 1346.11  4835.8 1334.79
  4851.5 1333.02    4873 1333.19  4894.5 1327.23  4931.7 1326.29  4947.4 1332.21
  4962.3  1328.6  4968.9 1324.47  5002.8    1323  5003.3  1322.5    5021    1323
  5064.8 1323.65  5101.3 1327.84  5123.5  1325.5  5152.5 1328.63  5178.4 1327.55
  5199.4 1331.07  5272.8 1336.65  5384.5 1347.57  5471.9 1352.82  5521.6 1352.94
#Mann= 3 ,-1 , 0
  4542.3     .05       0  5002.8     .03       0    5021     .05       0
Bank Sta=5002.8,5021
XS Rating Curve= 0 ,0
Exp/Cntr=0.3,0.1

Type RM Length L Ch R = 1 ,2249    ,544,544,544
BEGIN DESCRIPTION:
WALNUT SPRING CREEK 4.0
END DESCRIPTION:
XS GIS Cut Line= 3
      2777842.85      10162161.5      2778276.87      10161401.1
      2778805.67     10161153.12
#Sta/Elev= 30
    4441 1350.61  4682.7 1342.23  4875.7 1318.83  4918.9 1323.71  4983.7 1324.26
  5005.8 1317.39  5006.3 1316.89    5024 1317.39  5080.2 1318.65    5130 1326.88
  5198.3 1324.69  5268.8 1338.84  5367.8 1343.52  5470.1 1353.35  5515.8 1351.58
  5533.1 1342.76  5538.6 1336.83  5584.2 1348.73  5613.4 1346.71    5744 1370.05
    5757 1377.87  5772.3 1381.74  5801.2 1399.14  5840.8 1407.76  5856.4 1421.82
  5863.6 1420.62  5869.1  1433.1  5878.5 1439.06    5892 1443.51  5900.6 1439.12
#Mann= 3 ,-1 , 0
    4441     .05       0  5005.8     .05       0    5024     .05       0
Bank Sta=5005.8,5024
XS Rating Curve= 0 ,0
Exp/Cntr=0.3,0.1

Type RM Length L Ch R = 1 ,1705    ,535,535,535
BEGIN DESCRIPTION:
WALNUT SPRING CREEK 3.0
END DESCRIPTION:
XS GIS Cut Line= 3
      2778405.69     10162353.11       2778688.1     10161732.43
      2778825.08     10161357.05
#Sta/Elev= 30
  4484.5 1356.48  4539.4 1349.13  4786.5 1332.66  4809.5 1328.99  4861.1 1327.65
  4930.3 1315.51  4980.7 1314.12  4981.2 1313.62    4999 1314.12  5125.8 1316.78
  5168.7 1321.76    5203 1332.65  5218.9 1333.34  5233.6 1333.17  5272.1 1321.48
  5289.4  1318.8  5314.6 1322.09  5345.1 1332.22  5387.6 1334.07  5411.6 1334.95
    5462 1345.42  5467.4 1343.74  5487.4 1346.24  5492.6 1348.14  5497.9 1345.49
  5523.1 1352.76  5528.5 1349.48  5548.4 1355.98  5553.7 1355.07    5566 1362.38
#Mann= 5 ,-1 , 0
  4484.5     .05       0  4980.7     .05       0    4999     .05       0
  5387.6     .12       0  5487.4     .05       0
Bank Sta=4980.7,4999
XS Rating Curve= 0 ,0
Exp/Cntr=0.3,0.1

Type RM Length L Ch R = 1 ,1170    ,489,489,489
BEGIN DESCRIPTION:
WALNUT SPRING CREEK 2.0
END DESCRIPTION:
XS GIS Cut Line= 3
      2778995.62     10162543.47      2779205.68     10161753.11
      2779252.36      10161316.2
#Sta/Elev= 30
  4480.2 1343.71    4522 1343.67  4578.3 1337.88  4646.1 1336.39  4733.8 1331.41
    4774    1327  4801.3 1321.77  4832.4 1324.32  4935.8 1322.16  4946.2 1321.27
  4964.4 1315.47  4987.6 1312.25  4988.7 1310.07  4989.2 1309.57  5007.1 1310.07
  5184.2 1312.64  5205.4 1316.08  5256.6  1314.2    5267 1316.34  5287.7 1326.69
  5295.4 1327.57  5398.6 1328.28  5436.5 1330.14    5479 1329.19  5569.5  1334.3
  5599.7  1333.5  5631.2  1336.7    5650 1340.45  5723.5 1345.66  5737.4 1348.08
#Mann= 3 ,-1 , 0
  4480.2     .05       0  4988.7     .03       0  5007.1     .05       0
Bank Sta=4988.7,5007.1
XS Rating Curve= 0 ,0
Exp/Cntr=0.3,0.1

Type RM Length L Ch R = 1 ,681     ,0,0,0
BEGIN DESCRIPTION:
WALNUT SPRING CREEK 1.0
END DESCRIPTION:
XS GIS Cut Line= 4
      2779155.69     10162903.11      2779383.98      10162524.4
        2779657.      10162071.5      2779644.92     10161730.94
#Sta/Elev= 30
  4218.2 1382.92  4221.1 1382.92  4231.8 1376.01  4241.5 1367.66  4247.3 1366.73
  4253.2 1352.01  4262.8 1348.36  4268.7 1351.02  4284.2 1347.44    4290 1348.67
  4321.1 1341.07    4370 1334.93  4385.2 1331.13  4400.7 1333.02  4406.5 1330.64
  4437.6 1333.79  4486.8 1327.66  4532.7 1329.17  4860.4 1326.37  4872.5 1325.22
  4909.4 1314.57  4946.3 1308.53  5010.8  1306.1  5011.3  1305.6  5029.2  1306.1
  5115.2 1308.35  5185.4 1323.31  5267.7 1319.06  5365.1 1327.87    5530 1332.86
#Mann= 3 ,-1 , 0
  4218.2     .05       0  5010.8     .03       0  5029.2     .05       0
Bank Sta=5010.8,5029.2
XS Rating Curve= 0 ,0
Exp/Cntr=0.3,0.1

Chan Stop Cuts=-1
Use User Specified Reach Order=0
Composite Channel Slope=5