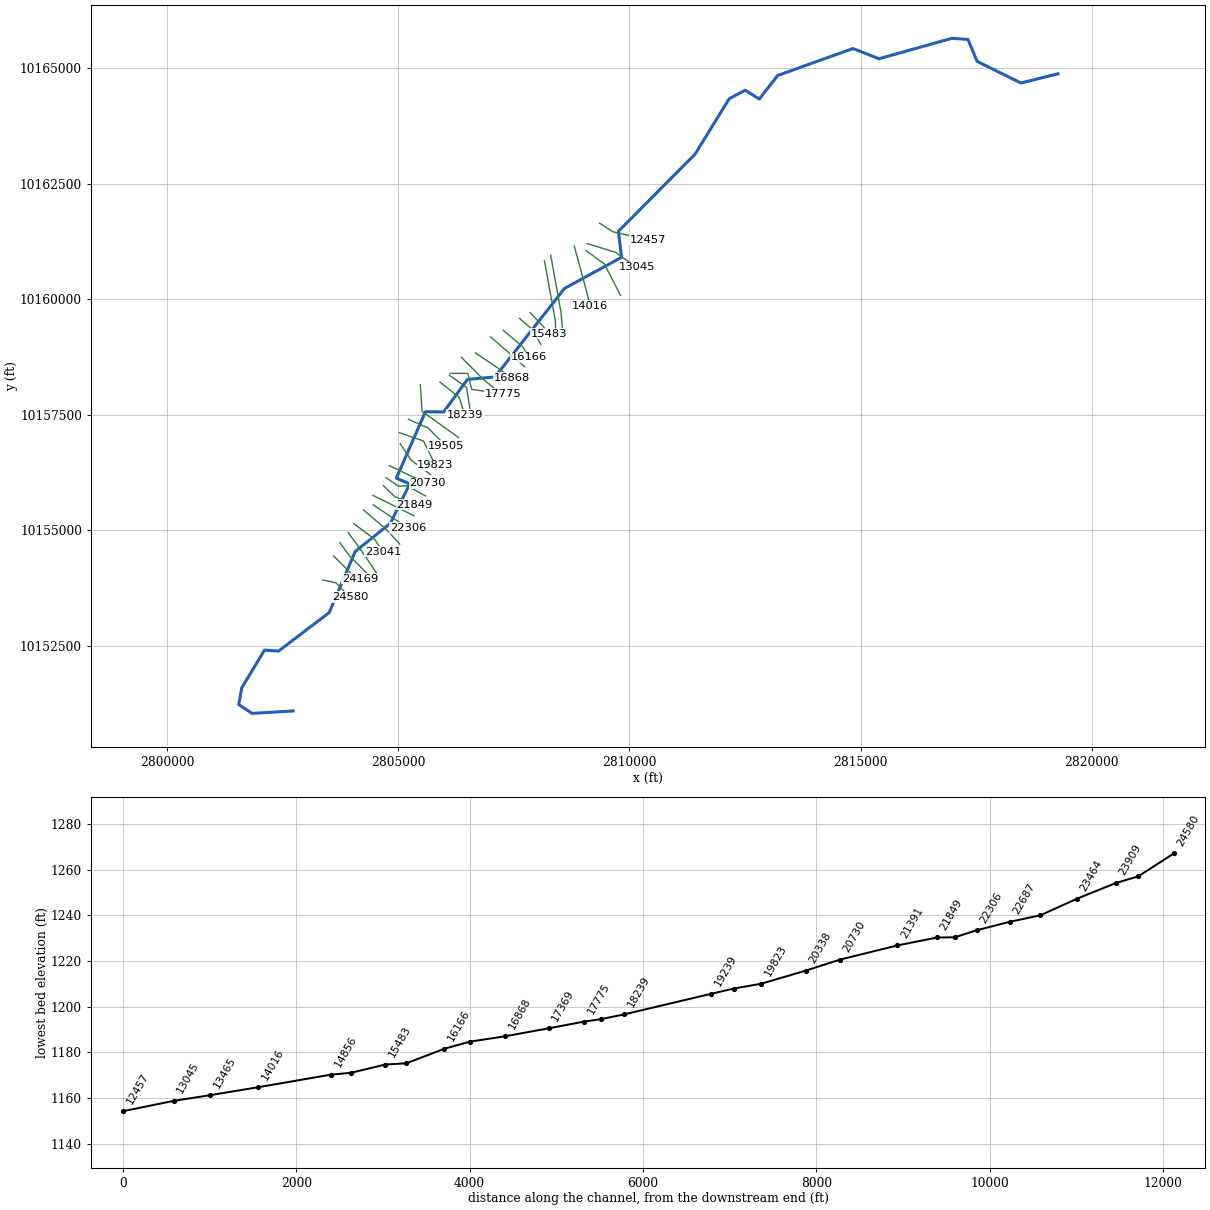
--- WILLOW BRANCH.prj (project) ---

Proj Title=WILLOW BRANCH Base Level Engineering
Current Plan=p01
Default Exp/Contr=0.3,0.1
English Units
Geom File=g01
Flow File=f01
Plan File=p01
Y Axis Title=Elevation
X Axis Title(PF)=Main Channel Distance
X Axis Title(XS)=Station
BEGIN DESCRIPTION:
WILLOW BRANCH
END DESCRIPTION:
DSS Export Rating Curves= 0
DSS Export Rating Curve Sorted= 0
DSS Export Volume Flow Curves= 0
DXF OffsetX= 0
DXF OffsetY= 0
DXF ScaleX= 1
DXF ScaleY= 10

--- WILLOW BRANCH.p01 (plan) ---

Plan Title=Multiple Run
Short Identifier=Multiple
Geom File=g01
Flow File=f01
Subcritical Flow
K Sum by GR= 0
Std Step Tol= 0.01
Critical Tol= 0.01
Num of Std Step Trials= 20
Max Error Tol= 0.3
Flow Tol Ratio= 0.001
Split Flow NTrial= 30
Split Flow Tol= 0.02
Split Flow Ratio= 0.02
Log Output Level= 0
Friction Slope Method= 1
Unsteady Friction Slope Method= 2
Unsteady Bridges Friction Slope Method= 1
Parabolic Critical Depth
Global Vel Dist=  1 , 1 , 1
Global Log Level= 0
CheckData=True
Encroach Param= -1, 0, 0, 0
BEGIN DESCRIPTION:
Multiple Run
END DESCRIPTION:

--- WILLOW BRANCH.f01 (steady flow) ---

Flow Title=Multiple
Number of Profiles=7
Profile Names=10-year,25-year,50-year,1pct_min,100-year,1pct_plu,500-year
River Rch & RM= WILLOW BRANCH,Reach-1,24580
     487     792    1718    1399    2433    4229    3541
River Rch & RM= WILLOW BRANCH,Reach-1,18239
     517     846    1778    1417    2516    4467    3654
River Rch & RM= WILLOW BRANCH,Reach-1,17369
    1070    1834    3854    2903    5560   10647    7983
River Rch & RM= WILLOW BRANCH,Reach-1,13465
    1763    3138    5985    4180    8687   18054   12329
Boundary for River Rch & Prof#=WILLOW BRANCH,Reach-1,1
Up Type=0
Dn Type=3
Dn Slope=0.005
Boundary for River Rch & Prof#=WILLOW BRANCH,Reach-1,2
Up Type=0
Dn Type=3
Dn Slope=0.005
Boundary for River Rch & Prof#=WILLOW BRANCH,Reach-1,3
Up Type=0
Dn Type=3
Dn Slope=0.005
Boundary for River Rch & Prof#=WILLOW BRANCH,Reach-1,4
Up Type=0
Dn Type=3
Dn Slope=0.005
Boundary for River Rch & Prof#=WILLOW BRANCH,Reach-1,5
Up Type=0
Dn Type=3
Dn Slope=0.005
Boundary for River Rch & Prof#=WILLOW BRANCH,Reach-1,6
Up Type=0
Dn Type=3
Dn Slope=0.005
Boundary for River Rch & Prof#=WILLOW BRANCH,Reach-1,7
Up Type=0
Dn Type=3
Dn Slope=0.005

--- WILLOW BRANCH.g01 (geometry) ---

Geom Title=Existing Conditions
Program Version=4.10

River Reach=WILLOW BRANCH   ,Reach-1
Reach XY= 30
        2802729.       10151086.      2801838.25       10151034.
      2801551.75       10151225.        2801617.       10151588.
        2802109.       10152403.       2802413.5       10152382.
       2803507.5       10153215.      2804070.25       10154537.
      2804832.25       10155148.      2805249.75       10155999.
        2804961.       10156126.       2805588.5       10157561.
      2805985.25       10157558.       2806497.5       10158261.
      2807093.75       10158315.      2808596.25       10160230.
       2809830.5       10160904.      2809762.75       10161467.
      2811422.75       10163139.       2812158.5       10164336.
      2812506.75       10164521.      2812808.75       10164329.
      2813207.25       10164839.      2814835.25       10165422.
        2815398.       10165201.      2816971.75       10165643.
      2817322.25       10165620.      2817519.75       10165145.
       2818469.5       10164676.        2819269.       10164876.

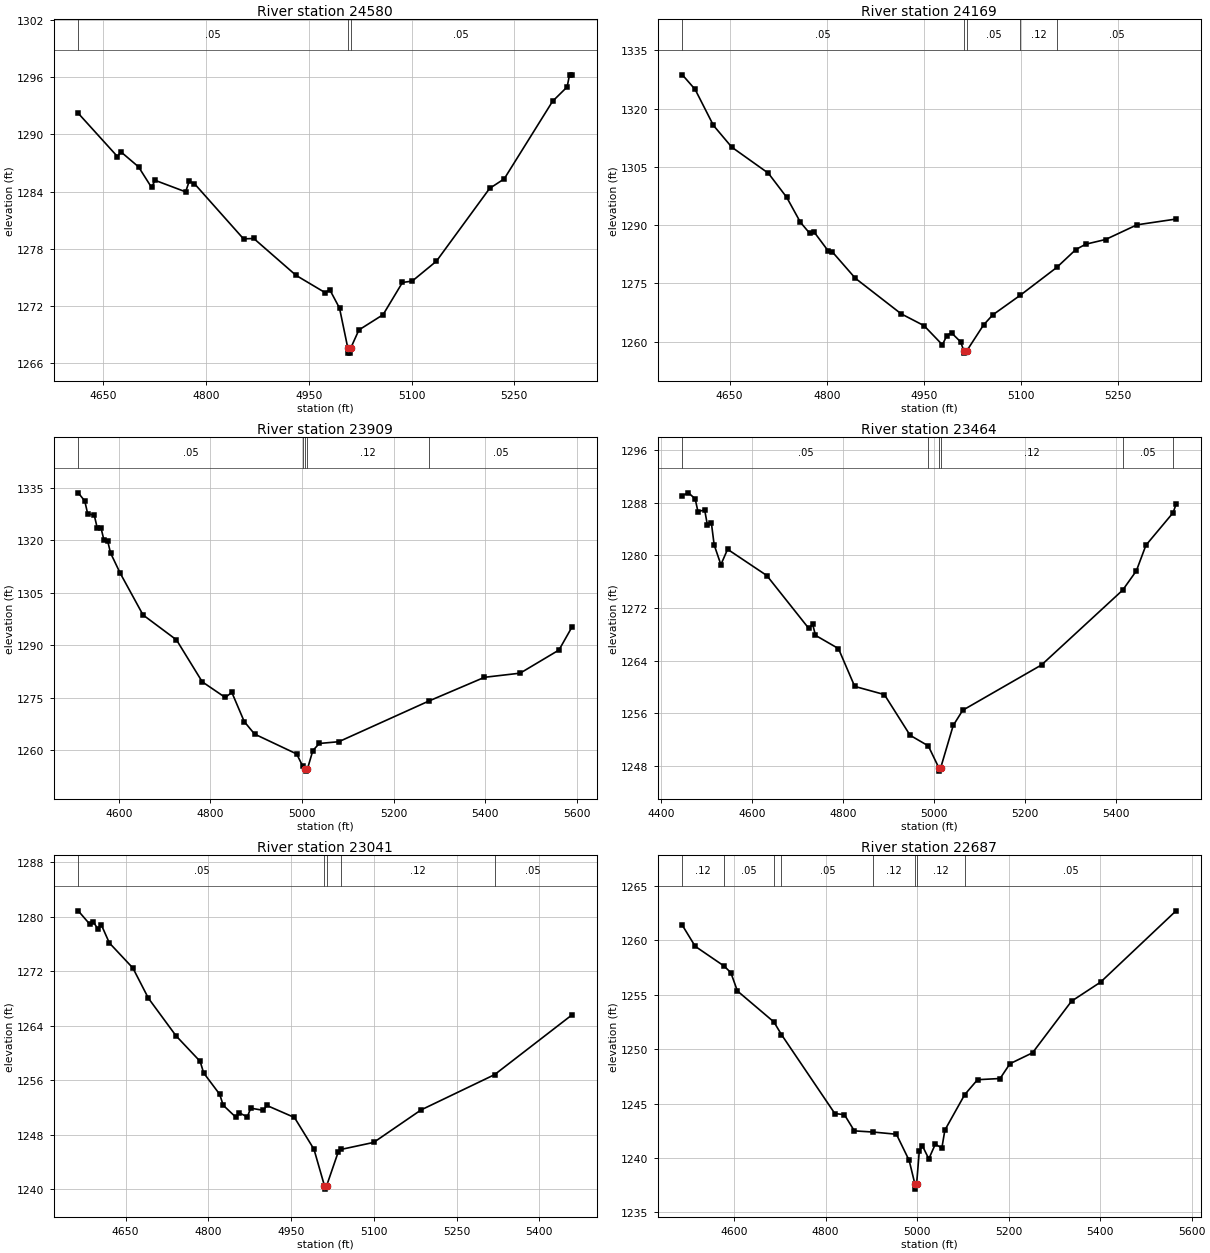
Type RM Length L Ch R = 1 ,24580   ,411,411,411
BEGIN DESCRIPTION:
WILLOW BRANCH 43.0
END DESCRIPTION:
XS GIS Cut Line= 3
      2803369.49     10153920.97      2803649.42     10153861.94
      2803955.67     10153553.13
#Sta/Elev= 30
  4613.1 1292.21  4670.4 1287.67  4675.5 1288.16  4701.2 1286.59  4720.2 1284.43
  4725.3 1285.18    4770 1283.97  4775.1 1285.07  4782.9 1284.82  4854.5 1279.04
  4869.5 1279.08  4931.1 1275.22  4973.5 1273.41  4980.6 1273.69  4994.7 1271.78
  5006.9 1267.56  5007.1 1267.06  5010.6 1267.06  5010.9 1267.56    5023 1269.49
  5058.3 1271.09  5086.6 1274.47  5100.8 1274.61  5136.2  1276.7  5213.9 1284.33
  5235.2 1285.33  5305.9 1293.47  5327.1 1294.97  5330.6 1296.24  5334.1 1296.24
#Mann= 3 ,-1 , 0
  4613.1     .05       0  5006.9     .05       0  5010.9     .05       0
Bank Sta=5006.9,5010.9
XS Rating Curve= 0 ,0
Exp/Cntr=0.3,0.1

Type RM Length L Ch R = 1 ,24169   ,260,260,260
BEGIN DESCRIPTION:
WILLOW BRANCH 42.0
END DESCRIPTION:
XS GIS Cut Line= 3
      2803603.87     10154439.19      2803976.25     10154069.41
      2804178.04     10153943.76
#Sta/Elev= 30
  4576.9 1328.71  4596.6 1324.96  4624.9 1315.68  4653.2 1310.08  4709.7 1303.37
    4738 1297.17  4759.3 1290.71  4773.4 1287.93  4780.5 1288.19  4801.7 1283.45
  4808.7 1283.07  4844.1  1276.3  4914.8 1267.15  4950.2 1264.09  4978.5 1259.17
  4985.5 1261.56  4992.6 1262.25  5006.7 1259.92  5011.8 1257.52  5012.1 1257.02
  5015.8 1257.52  5042.1 1264.28  5056.3 1266.87    5099 1271.95  5155.2  1279.1
  5184.6  1283.7  5199.9 1285.08  5230.6 1286.29    5279 1290.07  5339.4 1291.56
#Mann= 5 ,-1 , 0
  4576.9     .05       0  5011.8     .03       0  5015.8     .05       0
    5099     .12       0  5155.2     .05       0
Bank Sta=5011.8,5015.8
XS Rating Curve= 0 ,0
Exp/Cntr=0.3,0.1

Type RM Length L Ch R = 1 ,23909   ,445,445,445
BEGIN DESCRIPTION:
WILLOW BRANCH 41.0
END DESCRIPTION:
XS GIS Cut Line= 3
      2803739.26     10154725.67      2803958.02     10154431.39
        2804461.     10153928.41
#Sta/Elev= 30
  4511.5 1333.58  4525.8 1331.25    4532 1327.67  4546.6 1327.14  4552.9 1323.62
  4561.2 1323.58  4567.5 1320.15  4575.8 1319.81  4582.1  1316.4  4602.9 1310.69
    4653  1298.7    4726 1291.58  4782.3  1279.6  4832.4 1275.14    4847 1276.55
    4874 1268.24  4896.5 1264.68  4988.5 1258.99  5001.4 1255.58  5007.7 1254.59
  5007.9 1254.09  5011.7 1254.59  5023.8 1259.97  5037.9 1261.99  5080.4 1262.49
  5277.8 1274.15  5398.6 1280.89  5476.4 1282.07  5561.2 1288.68  5589.5 1295.22
#Mann= 5 ,-1 , 0
  4511.5     .05       0  5001.4     .12       0  5007.7     .05       0
  5011.7     .12       0  5277.8     .05       0
Bank Sta=5007.7,5011.7
XS Rating Curve= 0 ,0
Exp/Cntr=0.3,0.1

Type RM Length L Ch R = 1 ,23464   ,423,423,423
BEGIN DESCRIPTION:
WILLOW BRANCH 40.0
END DESCRIPTION:
XS GIS Cut Line= 3
      2803921.56     10154947.02      2804293.96     10154426.18
      2804540.47     10154057.72
#Sta/Elev= 30
  4447.3 1289.07  4460.6 1289.49  4475.4 1288.59  4481.5 1286.65  4496.3 1286.89
  4502.4 1284.56    4511 1284.94  4517.1 1281.59  4531.9 1278.59  4546.6 1280.92
  4632.6 1276.94  4724.8 1268.91  4733.4 1269.51  4739.5 1267.86  4789.9 1265.85
  4825.6 1260.11  4890.7 1258.87  4947.2 1252.69  4987.1 1251.08  5010.3 1247.75
  5010.6 1247.25  5014.3 1247.75  5041.8 1254.18  5062.7 1256.49  5235.7 1263.37
  5413.7 1274.72  5443.8 1277.65  5464.8 1281.54  5524.2 1286.45  5530.9 1287.73
#Mann= 6 ,-1 , 0
  4447.3     .05       0  4987.1     .12       0  5010.3     .07       0
  5014.3     .12       0  5413.7     .05       0  5524.2     .12       0
Bank Sta=5010.3,5014.3
XS Rating Curve= 0 ,0
Exp/Cntr=0.3,0.1

Type RM Length L Ch R = 1 ,23041   ,354,354,354
BEGIN DESCRIPTION:
WILLOW BRANCH 39.0
END DESCRIPTION:
XS GIS Cut Line= 3
      2804036.15     10155142.33      2804486.13     10154806.85
      2804670.98     10154528.63
#Sta/Elev= 30
    4564 1280.87    4585  1278.9  4591.2 1279.26  4599.6 1278.22  4605.8 1278.83
  4620.4 1276.16  4663.2 1272.46  4691.3 1268.03  4741.3 1262.52  4785.1 1258.76
  4791.4 1257.07  4820.6 1253.92  4826.8 1252.33  4849.8 1250.56    4856 1251.21
  4870.6  1250.6  4876.8 1251.89  4899.8 1251.57    4906 1252.29  4956.1 1250.52
  4991.5 1245.86  5010.5  1240.5  5010.7    1240  5014.5  1240.5  5035.3 1245.41
    5040 1245.82  5099.8 1246.86  5185.7 1251.63    5319 1256.81  5459.3 1265.58
#Mann= 5 ,-1 , 0
    4564     .05       0  5010.5     .03       0  5014.5     .05       0
    5040     .12       0    5319     .05       0
Bank Sta=5010.5,5014.5
XS Rating Curve= 0 ,0
Exp/Cntr=0.3,0.1

Type RM Length L Ch R = 1 ,22687   ,381,381,381
BEGIN DESCRIPTION:
Mapping XS 021d3b16
END DESCRIPTION:
XS GIS Cut Line= 3
      2804249.65     10155436.63      2804744.48     10155014.73
      2805033.07     10154697.54
#Sta/Elev= 30
  4486.8 1261.37  4514.9 1259.44  4578.3 1257.62  4592.8 1257.02  4607.1 1255.34
    4687 1252.49  4703.3 1251.34  4820.1 1244.08    4841 1243.98  4862.7 1242.49
  4904.6 1242.38  4954.7 1242.18  4982.6 1239.77  4994.9 1237.64  4995.2 1237.14
  4998.9 1237.64  5004.6  1240.6  5011.2 1241.14  5025.5 1239.92  5039.7 1241.27
    5054 1240.91  5060.6 1242.56    5104 1245.82    5132 1247.19  5181.3  1247.3
  5202.9 1248.66  5252.2 1249.66  5337.4  1254.4  5400.9 1256.15  5565.9  1262.7
#Mann= 8 ,-1 , 0
  4486.8     .12       0  4578.3     .05       0    4687     .12       0
  4703.3     .05       0  4904.6     .12       0  4994.9     .07       0
  4998.9     .12       0    5104     .05       0
Bank Sta=4994.9,4998.9
XS Rating Curve= 0 ,0
Exp/Cntr=0.3,0.1

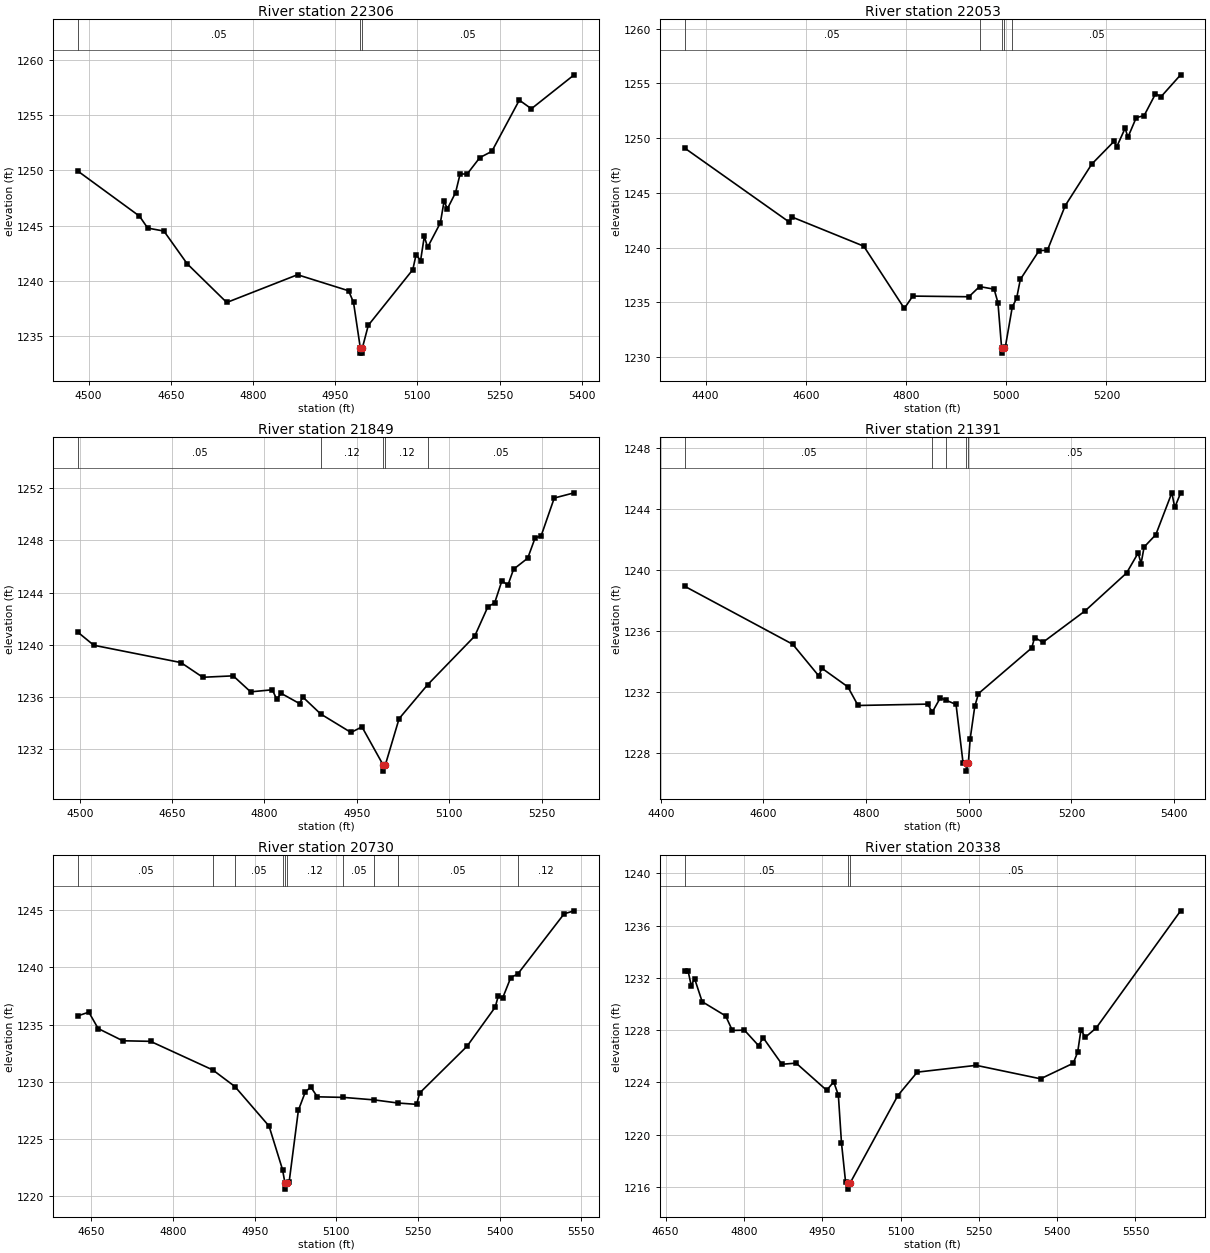
Type RM Length L Ch R = 1 ,22306   ,253,253,253
BEGIN DESCRIPTION:
Mapping XS 97465741
END DESCRIPTION:
XS GIS Cut Line= 2
      2804455.45     10155548.56      2805209.02     10155047.04
#Sta/Elev= 30
    4481  1249.9  4592.8 1245.85  4607.8 1244.77  4637.4  1244.5  4679.9 1241.54
  4752.1 1238.04  4881.3 1240.55  4974.5  1239.1  4983.5 1238.05  4995.8 1233.96
  4996.1 1233.46  4999.6 1233.46  4999.8 1233.96  5010.5 1235.98  5091.7 1241.01
  5097.7 1242.37  5105.9 1241.83  5112.7 1244.02  5118.7 1243.03    5142 1245.24
  5148.8 1247.21  5154.8 1246.51  5169.8 1247.98    5178 1249.66  5190.9 1249.66
    5214 1251.14    5236 1251.71  5286.1 1256.34  5308.1 1255.56  5386.2 1258.63
#Mann= 3 ,-1 , 0
    4481     .05       0  4995.8     .05       0  4999.8     .05       0
Bank Sta=4995.8,4999.8
XS Rating Curve= 0 ,0
Exp/Cntr=0.3,0.1

Type RM Length L Ch R = 1 ,22053   ,204,204,204
BEGIN DESCRIPTION:
WILLOW BRANCH 38.0
END DESCRIPTION:
XS GIS Cut Line= 3
      2804455.38     10155751.72      2805096.04       10155434.
      2805340.43     10155307.94
#Sta/Elev= 30
  4358.1  1249.1  4566.9 1242.34  4572.4  1242.8  4715.6 1240.14  4796.6 1234.45
  4813.4 1235.58  4925.5 1235.52  4946.8 1236.45  4975.9 1236.21  4983.5 1234.98
  4990.8 1230.87    4991 1230.37  4994.8 1230.87  4998.4 1230.97  5012.1 1234.58
  5020.8 1235.38  5028.2  1237.1  5065.6 1239.73  5082.3 1239.77  5117.8 1243.84
  5170.9 1247.64  5215.2 1249.71  5220.8 1249.23  5237.4 1250.91    5243 1250.09
  5259.5 1251.87  5275.4 1252.07  5297.9 1254.04  5309.5 1253.81  5348.2 1255.79
#Mann= 5 ,-1 , 0
  4358.1     .05       0  4946.8     .12       0  4990.8     .07       0
  4994.8     .12       0  5012.1     .05       0
Bank Sta=4990.8,4994.8
XS Rating Curve= 0 ,0
Exp/Cntr=0.3,0.1

Type RM Length L Ch R = 1 ,21849   ,458,458,458
BEGIN DESCRIPTION:
WILLOW BRANCH 37.0
END DESCRIPTION:
XS GIS Cut Line= 3
      2804679.37     10155962.65      2804926.19     10155724.56
      2805355.69     10155553.11
#Sta/Elev= 30
  4497.6 1240.93  4522.9 1239.95  4664.4 1238.62  4699.9 1237.49  4749.3  1237.6
  4777.6 1236.37  4812.8 1236.53    4820  1235.8    4827 1236.26    4857 1235.47
  4862.4 1235.97  4891.4 1234.67  4940.6 1233.25  4958.4 1233.68  4992.5 1230.78
  4992.7 1230.28  4996.5 1230.78  5018.7 1234.31  5064.9 1236.91  5141.5 1240.65
    5163 1242.92  5173.8 1243.19  5185.8 1244.92  5195.3 1244.55  5204.6 1245.79
  5227.6 1246.64  5239.7 1248.21  5249.2 1248.33  5270.7 1251.26    5303 1251.66
#Mann= 5 ,-1 , 0
  4497.6     .05       0  4891.4     .12       0  4992.5     .07       0
  4996.5     .12       0  5064.9     .05       0
Bank Sta=4992.5,4996.5
XS Rating Curve= 0 ,0
Exp/Cntr=0.3,0.1

Type RM Length L Ch R = 1 ,21391   ,661,661,661
BEGIN DESCRIPTION:
Mapping XS 970d0f6c
END DESCRIPTION:
XS GIS Cut Line= 4
      2804736.63     10156137.15       2805007.5     10155949.62
      2805184.58     10155960.04      2805588.19     10155741.31
#Sta/Elev= 30
  4446.7 1238.92  4657.1 1235.12  4707.8 1233.05  4713.9 1233.55  4764.5 1232.33
  4784.3 1231.11  4920.2  1231.2  4928.8 1230.67  4944.6 1231.61  4955.9 1231.45
  4975.2 1231.18  4988.9 1227.34  4995.1 1227.31  4995.3 1226.81  4999.1 1227.31
  5002.8 1228.94  5011.7 1231.05  5018.9 1231.89  5122.6 1234.88  5128.3 1235.56
  5144.5 1235.25  5226.3  1237.3  5307.4 1239.79  5329.9  1241.1  5335.6 1240.41
  5341.5 1241.49  5364.3  1242.3  5395.5 1245.04  5401.2 1244.08  5412.6 1245.03
#Mann= 5 ,-1 , 0
  4446.7     .05       0  4928.8     .12       0  4955.9     .05       0
  4995.1     .05       0  4999.1     .05       0
Bank Sta=4995.1,4999.1
XS Rating Curve= 0 ,0
Exp/Cntr=0.3,0.1

Type RM Length L Ch R = 1 ,20730   ,392,392,392
BEGIN DESCRIPTION:
WILLOW BRANCH 36.0
END DESCRIPTION:
XS GIS Cut Line= 3
      2804809.62     10156394.92      2805265.31     10156176.18
      2805635.11     10156009.51
#Sta/Elev= 30
  4625.9 1235.78  4645.4 1236.09  4662.5 1234.66  4707.8 1233.59  4758.7 1233.54
  4873.1 1231.04  4913.7 1229.59  4976.5 1226.13  5001.3 1222.32  5005.8 1221.12
    5006 1220.62  5009.8 1221.12  5013.3 1221.21  5030.4 1227.52    5043  1229.1
  5053.1 1229.55  5065.2 1228.69  5113.1 1228.64  5169.8 1228.42  5212.9 1228.15
  5247.7 1228.03  5253.1 1229.02  5340.2 1233.11    5392 1236.53  5397.5 1237.49
    5406 1237.37  5420.6 1239.12  5433.3 1239.42  5518.6 1244.69    5537 1244.95
#Mann= 10 ,-1 , 0
  4625.9     .05       0  4873.1     .12       0  4913.7     .05       0
  5001.3     .12       0  5005.8     .05       0  5009.8     .12       0
  5113.1     .05       0  5169.8     .12       0  5212.9     .05       0
  5433.3     .12       0
Bank Sta=5005.8,5009.8
XS Rating Curve= 0 ,0
Exp/Cntr=0.3,0.1

Type RM Length L Ch R = 1 ,20338   ,515,515,515
BEGIN DESCRIPTION:
WILLOW BRANCH 35.0
END DESCRIPTION:
XS GIS Cut Line= 3
      2805043.96     10156868.88      2805288.76     10156505.17
      2805701.71     10156203.03
#Sta/Elev= 30
  4686.4 1232.55  4692.9 1232.54  4698.9 1231.41  4705.4 1231.94  4719.9 1230.18
  4764.9 1229.09  4777.7 1227.98  4800.9    1228  4827.9 1226.82  4836.8 1227.42
  4872.8 1225.39  4899.9 1225.48  4958.5  1223.4  4971.9 1224.05  4980.8 1223.03
  4986.8 1219.38  4994.7 1216.36  4999.8 1216.34  5000.1 1215.84  5003.8 1216.34
  5094.8    1223    5132 1224.79  5244.9 1225.31  5368.2 1224.28  5430.8 1225.47
  5439.3 1226.32  5445.5 1228.01    5454 1227.46  5474.8 1228.17  5636.5 1237.13
#Mann= 3 ,-1 , 0
  4686.4     .05       0  4999.8     .05       0  5003.8     .05       0
Bank Sta=4999.8,5003.8
XS Rating Curve= 0 ,0
Exp/Cntr=0.3,0.1

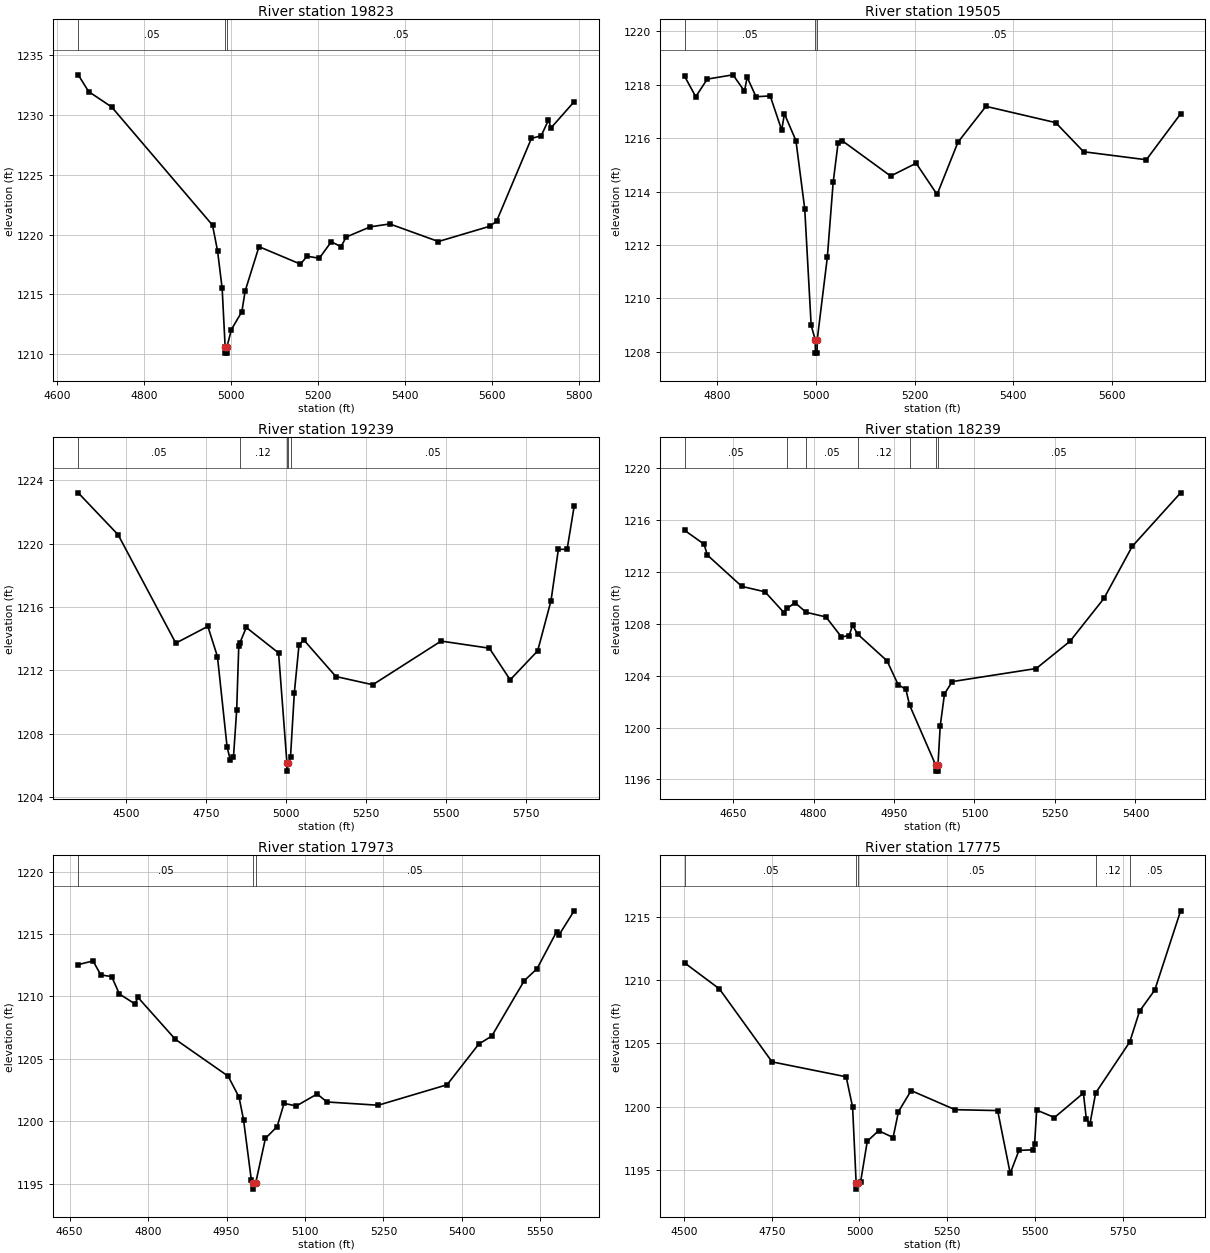
Type RM Length L Ch R = 1 ,19823   ,318,318,318
BEGIN DESCRIPTION:
WILLOW BRANCH 34.0
END DESCRIPTION:
XS GIS Cut Line= 3
      2805023.09     10157111.09      2805546.56     10156928.79
       2805805.7     10156403.09
#Sta/Elev= 30
  4648.7 1233.38  4672.6 1231.98  4725.6 1230.69  4957.5  1220.8  4969.1 1218.65
  4979.7  1215.5  4986.6 1210.59  4986.9 1210.09  4990.4 1210.09  4990.6 1210.59
  5000.9 1212.06    5025 1213.56  5032.6 1215.29  5064.4    1219  5159.7 1217.54
  5175.1  1218.2    5203 1218.03  5230.5  1219.4    5253 1219.01  5265.1 1219.81
  5320.3 1220.66  5365.2  1220.9  5476.9 1219.43  5595.4 1220.71  5610.7 1221.13
  5690.8 1228.06  5713.3 1228.28  5730.1  1229.6  5735.7 1228.93  5789.1 1231.13
#Mann= 3 ,-1 , 0
  4648.7     .05       0  4986.6     .05       0  4990.6     .05       0
Bank Sta=4986.6,4990.6
XS Rating Curve= 0 ,0
Exp/Cntr=0.3,0.1

Type RM Length L Ch R = 1 ,19505   ,266,266,266
BEGIN DESCRIPTION:
WILLOW BRANCH 33.0
END DESCRIPTION:
XS GIS Cut Line= 3
      2805221.02     10157397.55      2805645.26     10157210.72
      2806030.79     10156829.98
#Sta/Elev= 30
  4733.6 1218.31    4756 1217.55  4779.4 1218.21  4831.5 1218.37  4854.8 1217.76
  4860.3 1218.28  4878.2 1217.55    4907 1217.58  4930.3  1216.3  4935.8 1216.91
  4959.1 1215.91    4977 1213.35    4990 1208.99  4998.3 1208.45  4998.6 1207.95
  5002.1 1207.95  5002.3 1208.45  5022.8 1211.54  5034.6 1214.34  5044.6 1215.82
  5052.4 1215.91  5151.2 1214.58  5202.8 1215.06  5245.3 1213.89  5287.7 1215.85
  5344.3 1217.19  5485.7 1216.58  5542.3 1215.49  5669.5 1215.19    5739 1216.91
#Mann= 3 ,-1 , 0
  4733.6     .05       0  4998.3     .05       0  5002.3     .05       0
Bank Sta=4998.3,5002.3
XS Rating Curve= 0 ,0
Exp/Cntr=0.3,0.1

Type RM Length L Ch R = 1 ,19239   ,1000,1000,1000
BEGIN DESCRIPTION:
WILLOW BRANCH 32.0
END DESCRIPTION:
XS GIS Cut Line= 3
      2805478.85     10158147.56      2805515.31     10157572.02
      2806305.66     10157003.13
#Sta/Elev= 30
  4349.2 1223.22  4473.9 1220.57  4654.3 1213.72  4754.5 1214.78  4784.5 1212.87
  4814.6 1207.17  4824.6 1206.33  4834.6 1206.52  4844.6 1209.48  4851.2 1213.56
  4853.8  1213.7  4874.7 1214.71  4975.6  1213.1  5001.8 1206.13    5002 1205.63
  5005.8 1206.13  5012.9 1206.52  5024.9 1210.59  5039.4 1213.59  5054.1 1213.93
  5154.7 1211.61  5270.1 1211.09  5483.7 1213.85  5634.6  1213.4  5699.7  1211.4
  5785.6 1213.23  5827.3  1216.4  5850.4 1219.65  5877.7 1219.65  5899.7 1222.37
#Mann= 5 ,-1 , 0
  4349.2     .05       0  4853.8     .12       0  5001.8     .07       0
  5005.8     .12       0  5012.9     .05       0
Bank Sta=5001.8,5005.8
XS Rating Curve= 0 ,0
Exp/Cntr=0.3,0.1

Type RM Length L Ch R = 1 ,18239   ,266,266,266
BEGIN DESCRIPTION:
WILLOW BRANCH 31.0
END DESCRIPTION:
XS GIS Cut Line= 3
      2805905.69     10158203.11        2806320.      10157871.5
      2806442.13      10157497.3
#Sta/Elev= 30
  4559.9 1215.22  4595.9 1214.16  4602.3 1213.31  4666.3  1210.9  4709.6 1210.48
  4744.8 1208.88  4751.4 1209.22  4765.6 1209.64  4786.1  1208.9  4823.2 1208.54
    4852    1207  4866.4  1207.1  4872.8  1207.9  4882.3 1207.21  4936.9 1205.16
  4957.7 1203.32  4972.1 1202.95  4979.1 1201.73  5027.4 1197.14  5027.7 1196.64
  5031.7 1196.64    5032 1197.14  5036.1  1200.1  5044.1  1202.6  5058.5 1203.55
  5215.1 1204.56  5278.2 1206.67  5341.3 1209.97  5393.9 1213.98  5484.2 1218.12
#Mann= 7 ,-1 , 0
  4559.9     .05       0  4751.4     .12       0  4786.1     .05       0
  4882.3     .12       0  4979.1     .05       0  5027.4     .03       0
    5032     .05       0
Bank Sta=5027.4,5032
XS Rating Curve= 0 ,0
Exp/Cntr=0.3,0.1

Type RM Length L Ch R = 1 ,17973   ,198,198,198
BEGIN DESCRIPTION:
WILLOW BRANCH 30.0
END DESCRIPTION:
XS GIS Cut Line= 3
      2806105.65     10158353.14      2806478.01     10158088.34
      2806555.68     10157603.14
#Sta/Elev= 30
  4666.4 1212.55  4694.7 1212.85  4709.5 1211.73  4730.4 1211.59  4745.1  1210.2
  4774.7 1209.41  4780.8 1209.92  4852.1 1206.57    4953 1203.62  4973.9 1201.94
  4982.5 1200.13  4997.3 1195.34  5001.1 1195.07  5001.4 1194.57  5005.8 1195.07
  5024.3 1198.63  5046.8 1199.58    5060 1201.44  5083.4 1201.23  5123.3 1202.19
    5142 1201.55    5240 1201.29  5371.7 1202.93  5432.4 1206.19  5457.2 1206.83
  5519.2 1211.26  5543.8 1212.23  5581.2 1215.19  5586.2 1214.96  5614.7 1216.86
#Mann= 3 ,-1 , 0
  4666.4     .05       0  5001.1     .03       0  5005.8     .05       0
Bank Sta=5001.1,5005.8
XS Rating Curve= 0 ,0
Exp/Cntr=0.3,0.1

Type RM Length L Ch R = 1 ,17775   ,406,406,406
BEGIN DESCRIPTION:
Mapping XS b6e34120
END DESCRIPTION:
XS GIS Cut Line= 4
      2806126.81     10158392.12      2806507.02     10158390.73
      2806589.98     10158046.47      2807261.32     10157947.01
#Sta/Elev= 30
    4502 1211.36  4600.9 1209.31  4750.9 1203.54  4962.1 1202.36  4980.4 1199.97
  4990.5 1193.98  4990.8 1193.48  4995.4 1193.98  5003.2 1194.05  5022.3 1197.27
  5054.6  1198.1  5095.8 1197.56  5111.2 1199.61  5147.2 1201.27  5272.4 1199.76
  5393.7 1199.69  5429.5 1194.73  5454.4 1196.54  5493.9 1196.59    5499 1197.07
  5504.9 1199.73  5555.5 1199.14    5638 1201.07  5646.5    1199  5656.6 1198.63
  5672.9 1201.08    5770 1205.11  5798.1 1207.55  5841.4 1209.22    5915 1215.48
#Mann= 5 ,-1 , 0
    4502     .05       0  4990.5     .03       0  4995.4     .05       0
  5672.9     .12       0    5770     .05       0
Bank Sta=4990.5,4995.4
XS Rating Curve= 0 ,0
Exp/Cntr=0.3,0.1

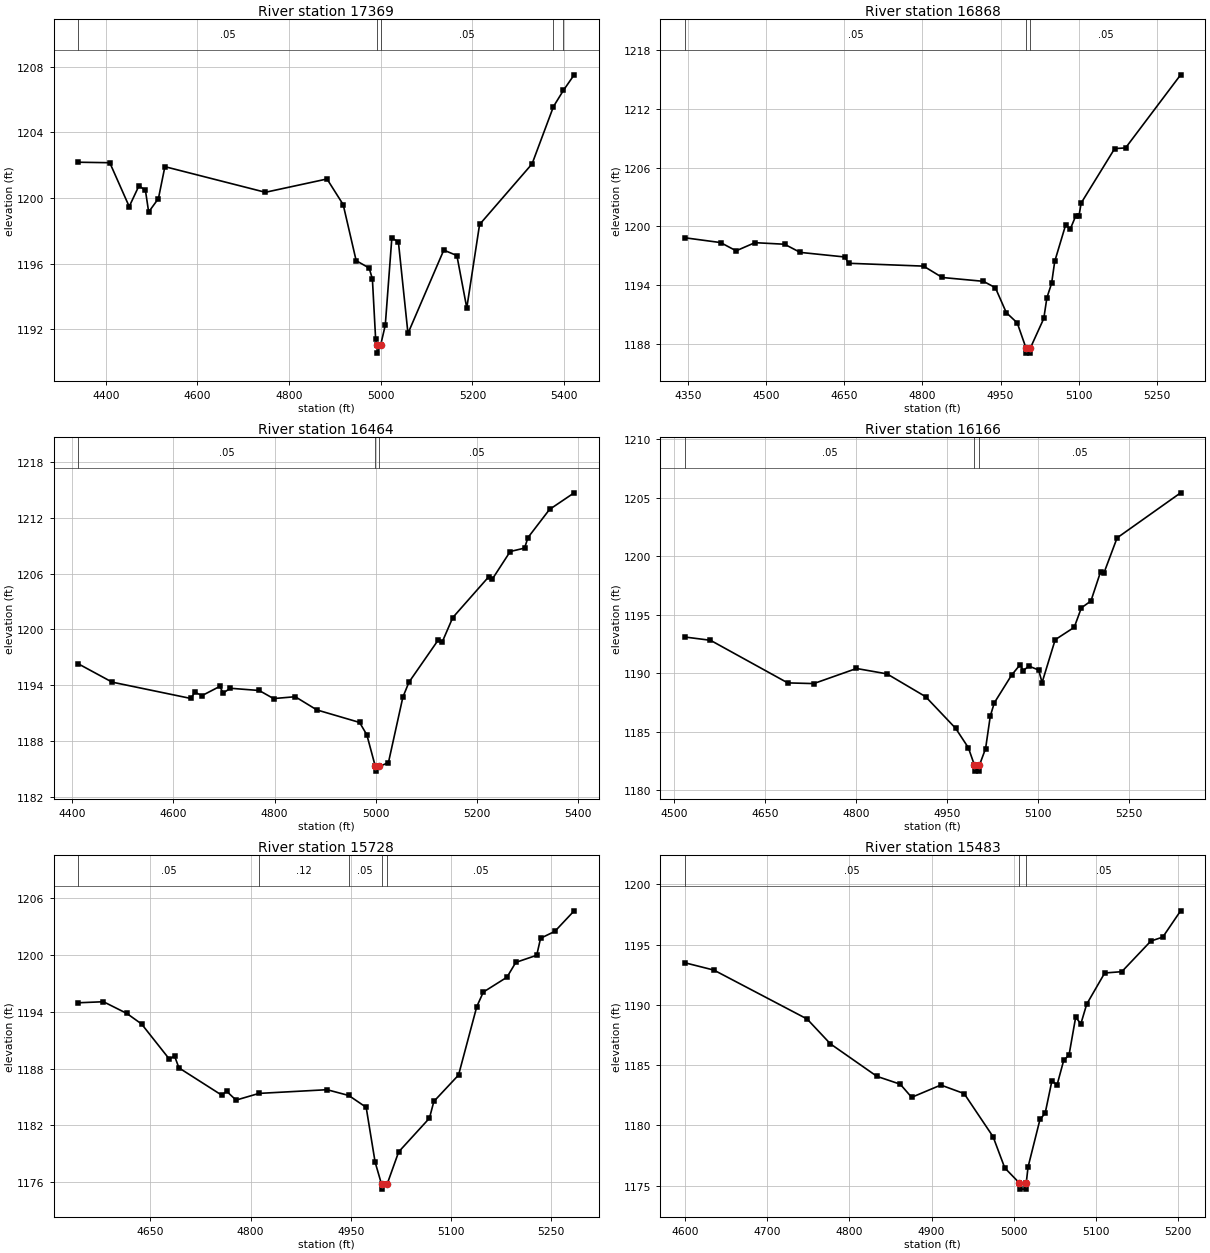
Type RM Length L Ch R = 1 ,17369   ,501,501,501
BEGIN DESCRIPTION:
WILLOW BRANCH 29.0
END DESCRIPTION:
XS GIS Cut Line= 3
      2806366.16     10158740.62       2806831.5       10158273.
      2807155.67     10158003.13
#Sta/Elev= 30
  4340.3 1202.18  4408.9 1202.15  4451.3 1199.48  4472.6 1200.75  4486.7 1200.46
  4493.7 1199.15    4515 1199.97  4529.1 1201.91  4748.3 1200.35  4882.7 1201.16
    4918  1199.6  4946.3 1196.19  4974.6 1195.74  4981.7 1195.08  4988.7 1191.45
  4991.8 1191.06  4992.3 1190.56  4999.8 1191.06  5009.8 1192.26  5024.1 1197.56
  5038.4 1197.34  5059.3 1191.76  5137.4 1196.83    5166  1196.5  5187.6 1193.31
  5215.5 1198.39    5330 1202.08  5376.7 1205.57  5398.5 1206.56  5421.8  1207.5
#Mann= 5 ,-1 , 0
  4340.3     .05       0  4991.8     .03       0  4999.8     .05       0
  5376.7     .12       0  5398.5     .05       0
Bank Sta=4991.8,4999.8
XS Rating Curve= 0 ,0
Exp/Cntr=0.3,0.1

Type RM Length L Ch R = 1 ,16868   ,404,404,404
BEGIN DESCRIPTION:
WILLOW BRANCH 28.0
END DESCRIPTION:
XS GIS Cut Line= 3
      2806671.54     10158835.05      2807293.96     10158413.16
      2807451.73      10158291.6
#Sta/Elev= 30
  4344.2 1198.84  4412.8 1198.35  4442.7 1197.51  4478.7 1198.34  4535.6 1198.18
  4565.5 1197.35  4651.2 1196.88  4658.4 1196.24  4802.2 1195.95  4838.1 1194.79
    4917  1194.4  4939.9 1193.75  4960.9 1191.21  4981.9 1190.16  4998.8 1187.58
  4999.3 1187.08  5006.4 1187.08  5006.9 1187.58  5032.8 1190.61  5038.8 1192.73
  5047.8 1194.19  5053.8 1196.43  5074.8 1200.16  5083.7 1199.74  5094.1 1201.06
  5100.3 1201.06  5104.5 1202.38  5168.8 1207.93  5189.7    1208  5295.3 1215.45
#Mann= 3 ,-1 , 0
  4344.2     .05       0  4998.8     .03       0  5006.9     .05       0
Bank Sta=4998.8,5006.9
XS Rating Curve= 0 ,0
Exp/Cntr=0.3,0.1

Type RM Length L Ch R = 1 ,16464   ,298,298,298
BEGIN DESCRIPTION:
WILLOW BRANCH 27.0
END DESCRIPTION:
XS GIS Cut Line= 3
      2806999.66     10159181.41      2807494.79     10158751.01
      2807734.08     10158532.94
#Sta/Elev= 30
    4412  1196.3  4478.8 1194.33  4634.5 1192.57  4642.1 1193.25  4656.4 1192.88
  4691.5 1193.87  4698.2 1193.16  4712.4 1193.67  4769.4 1193.43  4797.8 1192.56
  4840.6 1192.76  4883.3 1191.34  4967.8 1189.99  4982.1 1188.66  4998.9 1185.25
  4999.4 1184.75    5007 1185.25  5024.8 1185.67  5053.3 1192.71  5065.3 1194.32
  5123.5 1198.89  5130.9 1198.63  5151.9 1201.28  5222.8 1205.66  5230.3 1205.44
  5265.4 1208.39  5293.8 1208.76  5300.5 1209.89  5343.1 1212.92  5391.8 1214.71
#Mann= 3 ,-1 , 0
    4412     .05       0  4998.9     .03       0    5007     .05       0
Bank Sta=4998.9,5007
XS Rating Curve= 0 ,0
Exp/Cntr=0.3,0.1

Type RM Length L Ch R = 1 ,16166   ,438,438,438
BEGIN DESCRIPTION:
Mapping XS ad442351
END DESCRIPTION:
XS GIS Cut Line= 3
      2807270.49     10159327.25       2807697.6     10158962.64
      2807825.22     10158741.27
#Sta/Elev= 30
  4517.4 1193.09  4559.7 1192.81    4687 1189.17  4729.9 1189.11  4800.3  1190.4
  4850.6 1189.94  4914.3 1187.99  4963.7 1185.29  4984.6 1183.64  4994.8 1182.13
  4995.3 1181.63  5002.4 1181.63  5002.9 1182.13  5013.1 1183.56  5020.8 1186.32
  5027.4 1187.46  5055.9 1189.83  5070.2 1190.74  5074.8 1190.22  5084.7  1190.6
  5100.5 1190.27  5106.2  1189.2  5127.8 1192.86  5159.2 1193.92  5170.9 1195.58
  5186.7 1196.17  5202.5 1198.65  5208.2 1198.57  5229.8 1201.56  5334.5 1205.41
#Mann= 3 ,-1 , 0
  4517.4     .05       0  4994.8     .03       0  5002.9     .05       0
Bank Sta=4994.8,5002.9
XS Rating Curve= 0 ,0
Exp/Cntr=0.3,0.1

Type RM Length L Ch R = 1 ,15728   ,245,245,245
BEGIN DESCRIPTION:
WILLOW BRANCH 26.0
END DESCRIPTION:
XS GIS Cut Line= 3
      2807622.05     10159582.46       2807885.1     10159358.48
      2808087.23     10159016.42
#Sta/Elev= 30
    4542 1194.96  4579.6 1195.07  4614.7 1193.83  4636.7 1192.72  4678.4    1189
  4686.1 1189.34  4692.7 1188.08  4756.9 1185.19  4764.1 1185.61  4778.3 1184.67
  4812.7 1185.38  4914.6 1185.77  4947.1 1185.16  4973.2 1183.91  4986.6 1178.12
  4996.3 1175.76  4996.8 1175.26  5004.5 1175.76  5021.9  1179.2    5068 1182.76
  5074.6 1184.53  5111.6 1187.32  5138.9 1194.55  5148.7 1196.09  5184.1 1197.66
  5197.4 1199.23  5228.7 1199.98  5234.5 1201.78  5255.9 1202.51  5284.8 1204.68
#Mann= 5 ,-1 , 0
    4542     .05       0  4812.7     .12       0  4947.1     .05       0
  4996.3     .05       0  5004.5     .05       0
Bank Sta=4996.3,5004.5
XS Rating Curve= 0 ,0
Exp/Cntr=0.3,0.1

Type RM Length L Ch R = 1 ,15483   ,392,392,392
BEGIN DESCRIPTION:
WILLOW BRANCH 25.0
END DESCRIPTION:
XS GIS Cut Line= 3
      2807855.65     10159703.14        2808131.       10159413.
      2808255.71     10159253.08
#Sta/Elev= 30
    4600  1193.5  4635.4 1192.89  4748.7 1188.83    4777 1186.77  4833.6 1184.07
  4861.9 1183.42  4875.8 1182.33  4911.3 1183.35  4939.6 1182.64  4974.8 1179.06
    4989 1176.47  5006.9 1175.21  5007.4 1174.71  5014.6 1174.71  5015.1 1175.21
  5017.3 1176.54  5031.8 1180.49  5038.1 1181.01  5046.3 1183.69  5052.6 1183.36
  5060.7 1185.41  5067.1 1185.83  5075.2 1188.98  5081.5 1188.43  5088.6 1190.06
  5110.5 1192.65  5131.3 1192.76  5166.6  1195.3  5181.1 1195.63  5202.8 1197.81
#Mann= 3 ,-1 , 0
    4600     .05       0  5006.9     .05       0  5015.1     .05       0
Bank Sta=5006.9,5015.1
XS Rating Curve= 0 ,0
Exp/Cntr=0.3,0.1

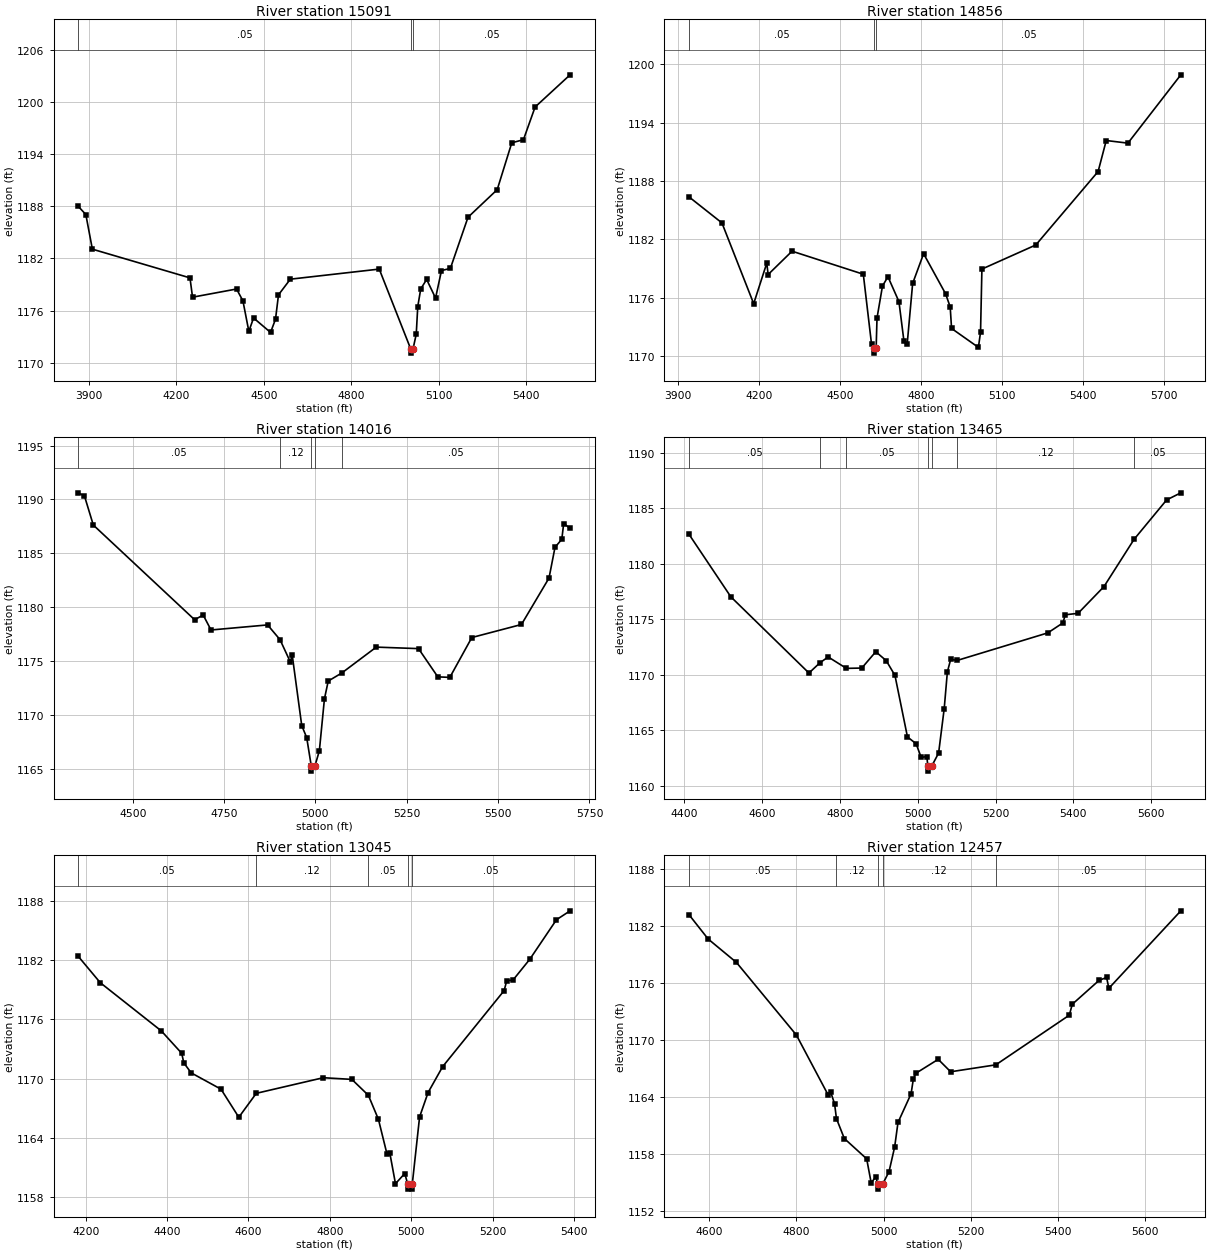
Type RM Length L Ch R = 1 ,15091   ,235,235,235
BEGIN DESCRIPTION:
WILLOW BRANCH 24.0
END DESCRIPTION:
XS GIS Cut Line= 3
      2808162.46     10160829.11      2808398.12     10159538.16
      2808408.54     10159163.19
#Sta/Elev= 30
  3863.1 1188.01  3889.5 1187.05  3911.9 1183.07  4246.7 1179.77  4255.5 1177.55
  4406.5 1178.49  4428.3 1177.13  4448.6 1173.63  4464.8 1175.16  4523.1  1173.5
  4540.1 1175.02  4550.3 1177.82  4590.9 1179.62  4895.9 1180.78  5003.6 1171.62
  5004.1 1171.12  5011.9 1171.62  5022.8  1173.3    5028 1176.47  5038.2  1178.5
  5058.5 1179.59    5089 1177.45  5109.4 1180.61  5139.9 1180.86  5200.4 1186.74
  5300.5 1189.91  5350.5  1195.3  5390.5 1195.65  5430.5 1199.41  5550.5 1203.11
#Mann= 3 ,-1 , 0
  3863.1     .05       0  5003.6     .03       0  5011.9     .05       0
Bank Sta=5003.6,5011.9
XS Rating Curve= 0 ,0
Exp/Cntr=0.3,0.1

Type RM Length L Ch R = 1 ,14856   ,840,840,840
BEGIN DESCRIPTION:
WILLOW BRANCH 23.0
END DESCRIPTION:
XS GIS Cut Line= 3
      2808299.17     10160949.62      2808517.92     10159730.87
      2808572.57     10159147.85
#Sta/Elev= 30
  3939.8 1186.37  4062.4 1183.68  4180.1 1175.37  4228.6 1179.54  4233.7 1178.37
  4322.3 1180.77  4586.5  1178.4    4617  1171.2  4625.8 1170.78  4626.3 1170.28
  4634.1 1170.78  4637.3 1173.89  4657.6 1177.19  4677.9 1178.14  4718.6 1175.58
  4737.3 1171.48    4749 1171.17  4769.4 1177.45    4810 1180.51  4891.3  1176.4
  4908.6 1175.04  4913.7 1172.82  5013.2 1170.87  5021.1 1172.43  5026.2 1178.93
    5226 1181.41    5457 1188.97  5487.1 1192.16  5567.5 1191.89  5763.6 1198.92
#Mann= 3 ,-1 , 0
  3939.8     .05       0  4625.8     .03       0  4634.1     .05       0
Bank Sta=4625.8,4634.1
XS Rating Curve= 0 ,0
Exp/Cntr=0.3,0.1

Type RM Length L Ch R = 1 ,14016   ,551,551,551
BEGIN DESCRIPTION:
WILLOW BRANCH 22.0
END DESCRIPTION:
XS GIS Cut Line= 3
      2808805.67     10161153.15       2808977.5       10160527.
      2809155.67     10159853.16
#Sta/Elev= 30
  4350.7 1190.61    4368 1190.32  4392.2 1187.62  4669.5 1178.83  4692.9 1179.27
  4714.3 1177.88  4869.2 1178.35  4903.2 1176.98  4931.4 1174.91  4936.5 1175.57
  4962.6 1169.01  4976.2 1167.89  4988.6 1165.28  4989.1 1164.78  4998.8 1165.28
  5010.8 1166.66  5024.7 1171.48  5035.1 1173.14  5072.3 1173.89  5166.6 1176.29
  5282.2 1176.15    5335 1173.53  5367.9 1173.48  5428.1 1177.18  5563.9 1178.39
  5639.3  1182.7  5655.7 1185.55  5674.3  1186.3  5679.5 1187.76    5697 1187.32
#Mann= 5 ,-1 , 0
  4350.7     .05       0  4903.2     .12       0  4988.6     .07       0
  4998.8     .12       0  5072.3     .05       0
Bank Sta=4988.6,4998.8
XS Rating Curve= 0 ,0
Exp/Cntr=0.3,0.1

Type RM Length L Ch R = 1 ,13465   ,420,420,420
BEGIN DESCRIPTION:
WILLOW BRANCH 21.0
END DESCRIPTION:
XS GIS Cut Line= 3
      2809055.65     10161053.14      2809460.62     10160759.52
      2809808.83      10160078.6
#Sta/Elev= 30
  4411.4 1182.68  4519.3 1177.03  4720.2 1170.16  4748.3 1171.08  4769.6 1171.61
  4816.5 1170.58  4856.1 1170.61    4892 1172.08  4918.8 1171.28  4941.3 1169.95
  4973.5  1164.4  4995.7 1163.79  5008.7 1162.56  5023.5 1162.63  5025.6 1161.82
  5026.1 1161.32  5036.6 1161.82  5053.6 1162.95    5068 1166.96  5076.1 1170.26
  5084.6 1171.39  5101.7  1171.3  5334.5 1173.78  5373.3 1174.68  5379.3 1175.41
  5412.2 1175.54  5478.8 1177.95  5556.2 1182.21  5639.9 1185.76  5676.4  1186.4
#Mann= 7 ,-1 , 0
  4411.4     .05       0  4748.3     .12       0  4816.5     .05       0
  5025.6     .05       0  5036.6     .05       0  5101.7     .12       0
  5556.2     .05       0
Bank Sta=5025.6,5036.6
XS Rating Curve= 0 ,0
Exp/Cntr=0.3,0.1

Type RM Length L Ch R = 1 ,13045   ,588,588,588
BEGIN DESCRIPTION:
WILLOW BRANCH 20.0
END DESCRIPTION:
XS GIS Cut Line= 3
      2809080.41     10161204.83       2809697.6     10161012.12
      2810158.56     10160689.19
#Sta/Elev= 30
  4181.3 1182.39  4235.7 1179.71  4385.9 1174.83  4435.9 1172.57  4441.1  1171.6
  4459.2 1170.59  4532.5 1168.94  4576.3  1166.1  4619.2 1168.52    4784  1170.1
  4854.2 1169.93  4894.8 1168.32  4919.6 1165.88  4940.5 1162.39  4947.6 1162.47
  4961.4 1159.38  4984.3 1160.41  4991.6 1159.33  4992.1 1158.83  5002.2 1158.83
  5002.7 1159.33  5020.7 1166.13  5041.6  1168.6  5077.4 1171.22  5228.5 1178.91
  5235.1 1179.93    5250 1179.96  5291.8 1182.09  5357.2 1186.08  5390.7 1186.98
#Mann= 5 ,-1 , 0
  4181.3     .05       0  4619.2     .12       0  4894.8     .05       0
  4991.6     .03       0  5002.7     .05       0
Bank Sta=4991.6,5002.7
XS Rating Curve= 0 ,0
Exp/Cntr=0.3,0.1

Type RM Length L Ch R = 1 ,12457   ,479,479,479
BEGIN DESCRIPTION:
WILLOW BRANCH 19.0
END DESCRIPTION:
XS GIS Cut Line= 3
      2809353.84     10161642.34      2809641.07     10161456.79
      2810408.51     10161280.36
#Sta/Elev= 30
  4553.1 1183.21  4597.4 1180.63  4662.4 1178.16  4799.9 1170.52  4872.5 1164.24
  4878.4 1164.55  4887.6 1163.28  4891.9 1161.72    4910 1159.62  4961.3 1157.48
  4971.6 1154.96  4982.7  1155.6  4986.5 1154.79    4987 1154.29  4997.7 1154.79
  5012.6 1156.13  5025.5 1158.72  5033.2 1161.31  5063.3 1164.34  5068.4 1165.88
  5074.2 1166.49  5125.5 1167.96  5154.1 1166.65  5257.8 1167.38  5426.5 1172.61
  5433.3 1173.76  5494.9 1176.28  5512.1 1176.58  5517.3 1175.44  5682.5  1183.6
#Mann= 5 ,-1 , 0
  4553.1     .05       0  4891.9     .12       0  4986.5     .07       0
  4997.7     .12       0  5257.8     .05       0
Bank Sta=4986.5,4997.7
XS Rating Curve= 0 ,0
Exp/Cntr=0.3,0.1