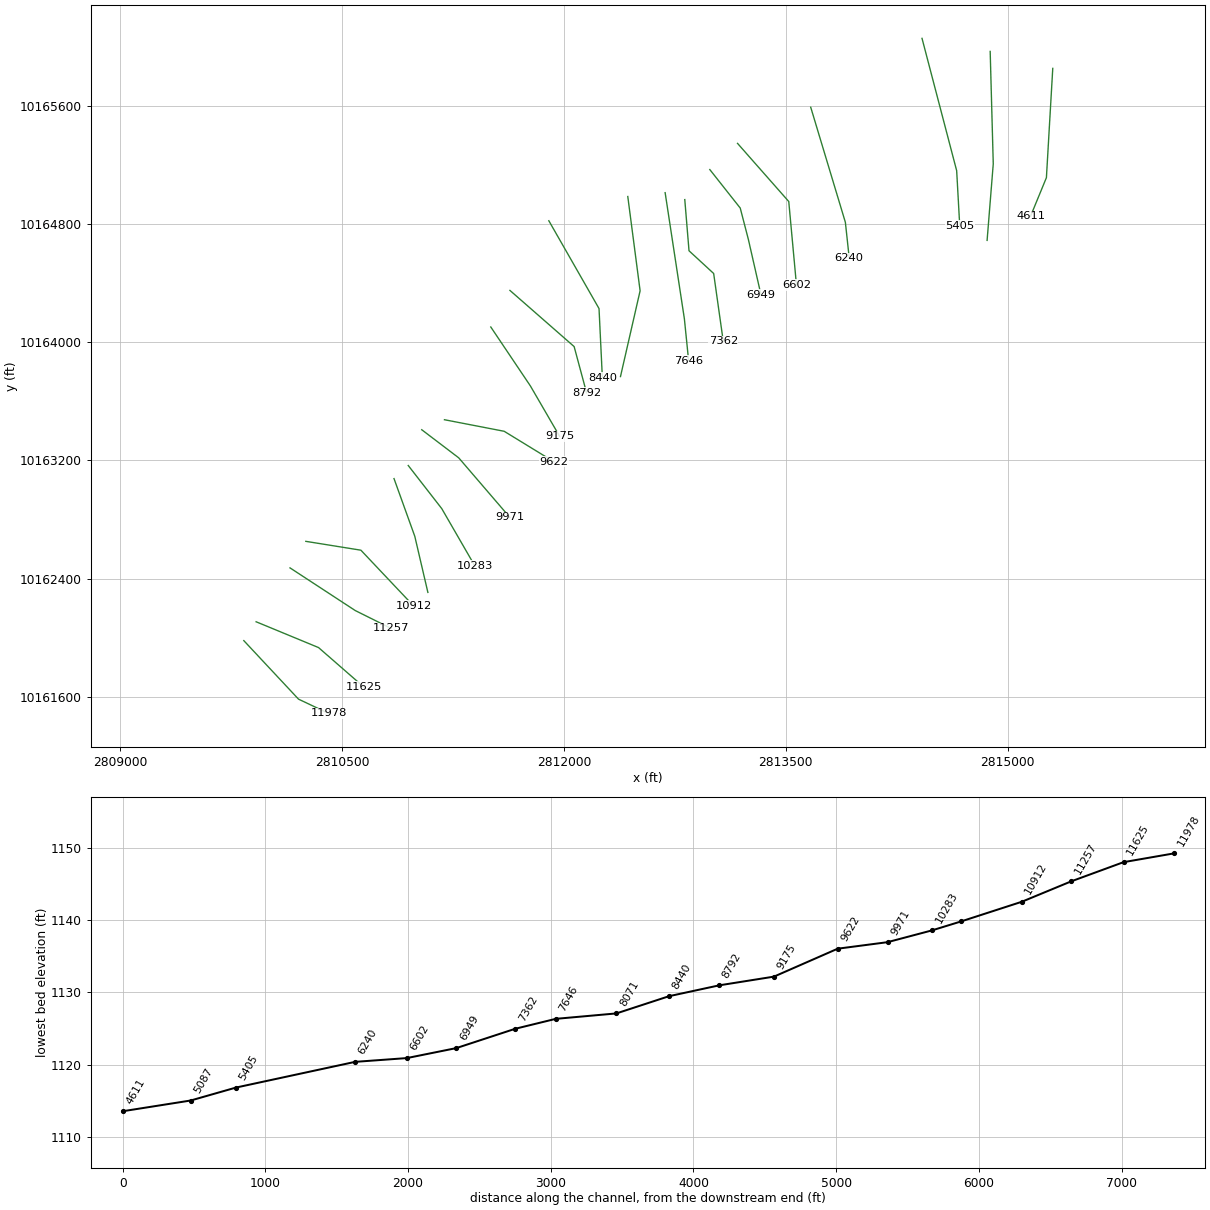
HEC-RAS study WILLOW BRANCH.prj: WILLOW BRANCH Base Level Engineering

--- WILLOW BRANCH.g01 (geometry) --- (continued)

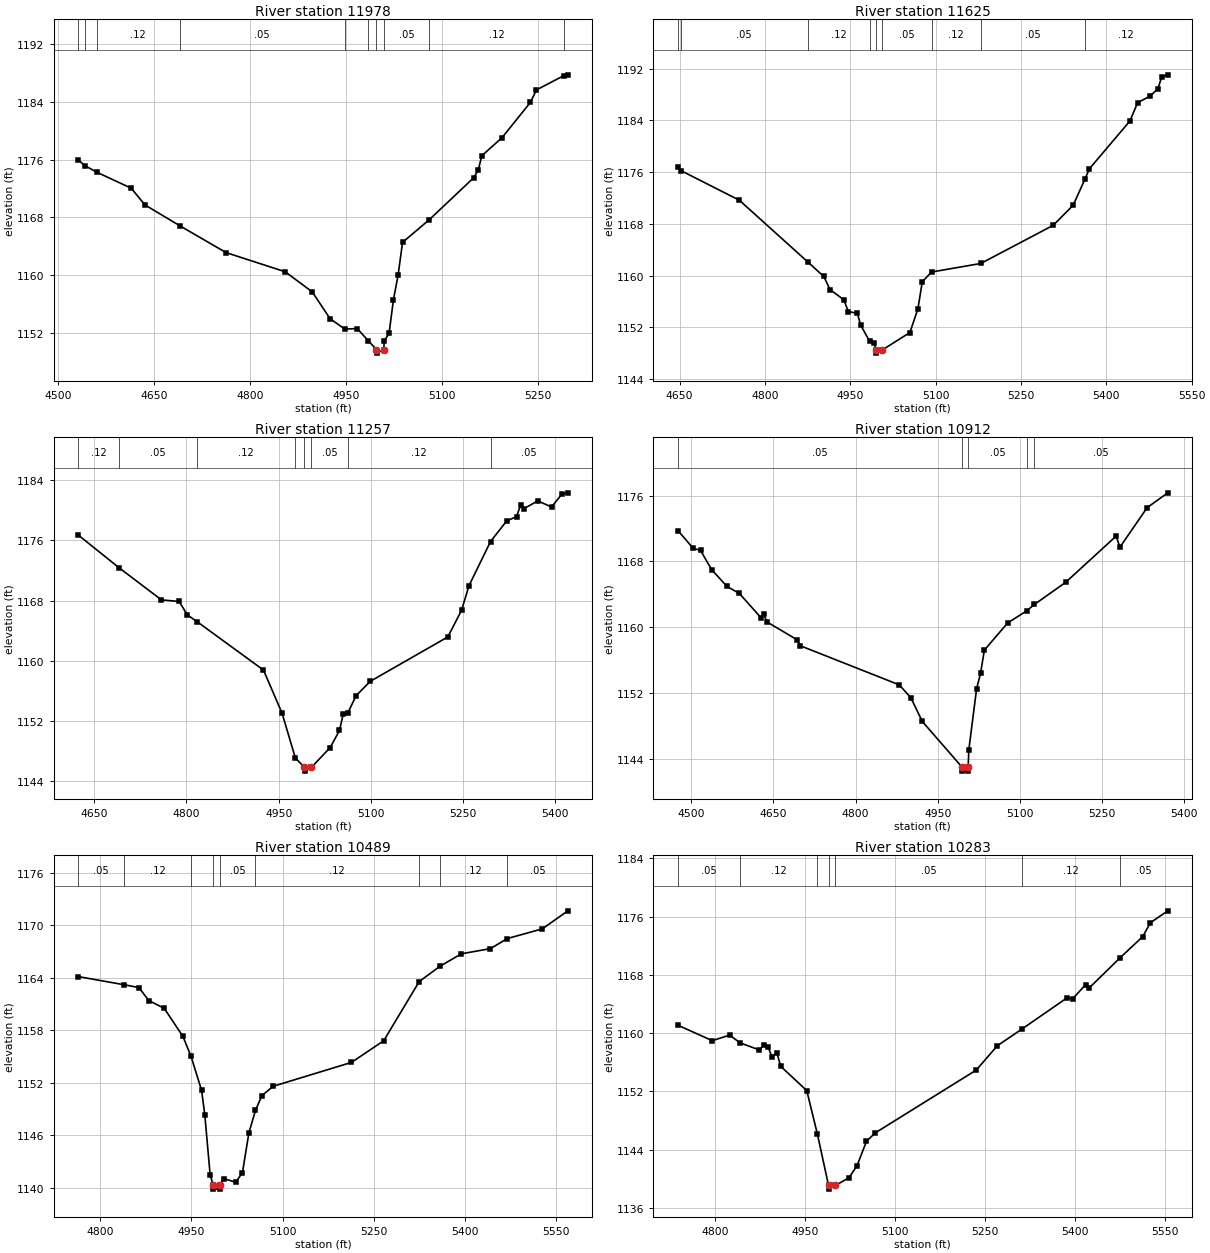
Type RM Length L Ch R = 1 ,11978   ,353,353,353
BEGIN DESCRIPTION:
WILLOW BRANCH 18.0
END DESCRIPTION:
XS GIS Cut Line= 3
      2809835.65     10161980.85      2810205.42     10161585.04
      2810408.56     10161488.67
#Sta/Elev= 30
  4530.6    1176  4541.3 1175.17  4560.1 1174.26  4613.8 1172.05  4635.3 1169.74
  4689.4 1166.87  4762.3 1163.13  4854.7 1160.48    4897  1157.7    4925 1153.98
    4948 1152.54  4967.5 1152.61  4985.1 1150.89  4997.6 1149.71  4998.1 1149.21
  5008.8 1149.71    5010 1150.92  5017.3 1151.95  5024.2 1156.63  5031.5 1160.05
  5038.4 1164.55  5080.5 1167.71    5150 1173.52    5157 1174.63  5162.5 1176.55
  5194.3 1179.07  5238.6 1183.95  5247.9 1185.66  5290.8 1187.64  5297.1 1187.75
#Mann= 10 ,-1 , 0
  4530.6     .12       0  4541.3     .05       0  4560.1     .12       0
  4689.4     .05       0    4948     .12       0  4985.1     .05       0
  4997.6     .03       0  5008.8     .05       0  5080.5     .12       0
  5290.8     .05       0
Bank Sta=4997.6,5008.8
XS Rating Curve= 0 ,0
Exp/Cntr=0.3,0.1

Type RM Length L Ch R = 1 ,11625   ,368,368,368
BEGIN DESCRIPTION:
WILLOW BRANCH 17.0
END DESCRIPTION:
XS GIS Cut Line= 3
      2809918.92     10162108.49      2810340.83       10161934.
      2810645.53     10161668.36
#Sta/Elev= 30
  4647.2 1176.75  4652.3 1176.25  4755.1 1171.66  4875.4 1162.11  4903.4 1159.87
  4914.7 1157.82  4938.6 1156.26  4946.7 1154.44  4962.6 1154.15  4968.3 1152.34
  4984.2 1149.81  4991.9 1149.64  4995.2  1148.5  4995.7    1148  5006.5  1148.5
  5054.9 1151.19    5069 1154.88  5076.6 1159.04  5092.9 1160.55  5179.4 1161.87
  5306.6 1167.77  5341.7 1170.88  5362.4  1174.9  5370.2 1176.51  5441.4 1183.91
  5455.1 1186.76  5476.5 1187.74  5490.7  1188.9  5497.4 1190.76    5508 1191.06
#Mann= 9 ,-1 , 0
  4647.2     .12       0  4652.3     .05       0  4875.4     .12       0
  4984.2     .05       0  4995.2     .03       0  5006.5     .05       0
  5092.9     .12       0  5179.4     .05       0  5362.4     .12       0
Bank Sta=4995.2,5006.5
XS Rating Curve= 0 ,0
Exp/Cntr=0.3,0.1

Type RM Length L Ch R = 1 ,11257   ,345,345,345
BEGIN DESCRIPTION:
WILLOW BRANCH 16.0
END DESCRIPTION:
XS GIS Cut Line= 3
      2810148.09     10162473.08      2810588.95     10162184.58
      2810830.44     10162064.19
#Sta/Elev= 30
  4623.6 1176.72  4690.6 1172.33  4759.3 1168.08    4788 1167.87  4801.5 1166.08
  4816.9 1165.21  4925.2 1158.76  4955.4 1153.04  4977.1 1147.08  4991.9 1145.84
  4992.4 1145.34  5003.2 1145.84  5033.7 1148.47  5048.8 1150.74  5054.8 1152.89
  5062.7 1153.12  5075.9 1155.36  5098.8 1157.26    5225 1163.16  5247.4  1166.7
  5259.4 1169.96  5294.5 1175.83  5320.9 1178.58  5336.8 1179.13  5343.3 1180.66
  5348.9  1180.2  5371.3 1181.23  5393.7 1180.42  5410.5 1182.13  5420.3  1182.3
#Mann= 8 ,-1 , 0
  4623.6     .12       0  4690.6     .05       0  4816.9     .12       0
  4977.1     .05       0  4991.9     .03       0  5003.2     .05       0
  5062.7     .12       0  5294.5     .05       0
Bank Sta=4991.9,5003.2
XS Rating Curve= 0 ,0
Exp/Cntr=0.3,0.1

Type RM Length L Ch R = 1 ,10912   ,423,423,423
BEGIN DESCRIPTION:
Mapping XS 4d82b002
END DESCRIPTION:
XS GIS Cut Line= 3
      2810254.92     10162652.74      2810627.29     10162592.85
      2810982.73     10162216.66
#Sta/Elev= 30
  4475.6 1171.76  4503.2 1169.62  4516.9 1169.34  4537.1 1167.02  4565.1 1164.97
  4587.8 1164.12    4627 1161.19    4632 1161.59  4638.4 1160.65  4693.9 1158.46
  4699.2 1157.76  4879.9 1153.01    4901 1151.45    4922 1148.56  4994.4 1143.03
  4994.9 1142.53  5005.2 1142.53  5005.7 1143.03    5007 1145.15  5021.1 1152.52
  5028.4 1154.42  5035.3 1157.23  5077.7 1160.52  5112.3 1161.99  5126.7 1162.78
  5183.7 1165.46    5276 1171.08  5282.9 1169.73  5332.6 1174.54  5370.3 1176.34
#Mann= 5 ,-1 , 0
  4475.6     .05       0  4994.4     .05       0  5005.7     .05       0
  5112.3     .12       0  5126.7     .05       0
Bank Sta=4994.4,5005.7
XS Rating Curve= 0 ,0
Exp/Cntr=0.3,0.1

Type RM Length L Ch R = 1 ,10489   ,206,206,206
BEGIN DESCRIPTION:
WILLOW BRANCH 15.0
END DESCRIPTION:
XS GIS Cut Line= 3
      2810851.24     10163077.24      2810991.87      10162686.6
      2811080.22     10162307.23
#Sta/Elev= 30
  4764.1 1164.12  4840.1 1163.18  4864.1 1162.86  4880.3 1161.38  4905.7 1160.49
  4936.4 1157.28  4949.7 1155.01  4967.1 1151.11  4972.4 1148.28  4981.1 1141.47
    4986 1140.33  4986.5 1139.83  4996.9 1139.83  4997.4 1140.33  5003.1 1141.04
  5023.2 1140.62  5034.2 1141.72  5044.8 1146.26  5055.6 1148.83  5066.1 1150.51
  5084.6 1151.58  5213.3 1154.31  5266.2 1156.78  5324.6 1163.55    5359 1165.31
  5393.9 1166.72  5441.6 1167.31  5469.3 1168.46  5526.8 1169.57  5568.8 1171.63
#Mann= 9 ,-1 , 0
  4764.1     .05       0  4840.1     .12       0  4949.7     .05       0
    4986     .05       0  4997.4     .05       0  5055.6     .12       0
  5324.6     .05       0    5359     .12       0  5469.3     .05       0
Bank Sta=4986,4997.4
XS Rating Curve= 0 ,0
Exp/Cntr=0.3,0.1

Type RM Length L Ch R = 1 ,10283   ,312,312,312
BEGIN DESCRIPTION:
WILLOW BRANCH 14.0
END DESCRIPTION:
XS GIS Cut Line= 3
      2810947.57     10163165.81      2811174.17      10162874.1
      2811397.53     10162487.11
#Sta/Elev= 30
  4738.6 1161.09  4795.8 1158.97  4824.7 1159.73  4842.6 1158.65  4874.5 1157.69
  4881.3 1158.36    4889 1158.05  4895.3 1156.77  4903.5 1157.31  4909.8 1155.45
  4953.3 1152.11  4971.1  1146.1  4989.6 1139.08  4990.1 1138.58    5001 1139.08
  5023.9 1140.16  5037.1 1141.82  5052.8 1145.15  5067.3  1146.3  5235.7 1154.93
  5270.8 1158.27  5312.1 1160.58  5386.5 1164.82  5396.5 1164.74  5418.1 1166.67
  5423.9 1166.21  5475.7 1170.38  5513.2 1173.27  5525.8 1175.16  5554.8  1176.8
#Mann= 7 ,-1 , 0
  4738.6     .05       0  4842.6     .12       0  4971.1     .05       0
  4989.6     .05       0    5001     .05       0  5312.1     .12       0
  5475.7     .05       0
Bank Sta=4989.6,5001
XS Rating Curve= 0 ,0
Exp/Cntr=0.3,0.1

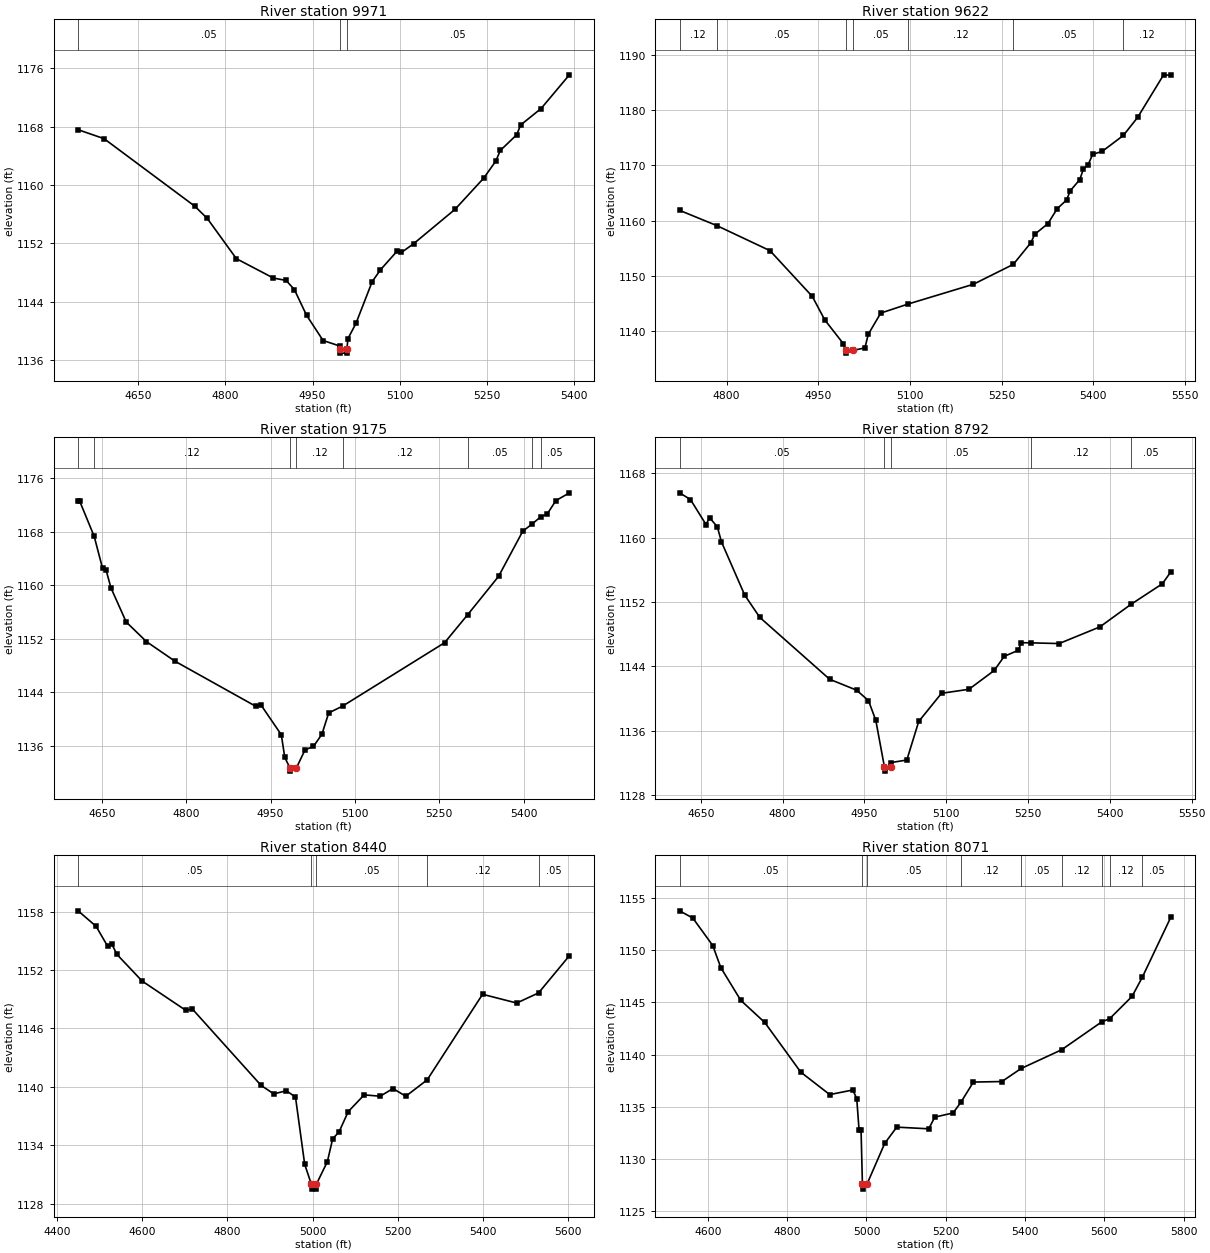
Type RM Length L Ch R = 1 ,9971    ,349,349,349
BEGIN DESCRIPTION:
Mapping XS 7ac2fe68
END DESCRIPTION:
XS GIS Cut Line= 3
      2811038.76     10163407.95      2811288.75     10163217.85
      2811635.08     10162814.23
#Sta/Elev= 30
  4546.4  1167.6  4591.1 1166.37  4747.1 1157.12  4768.7 1155.44  4818.9 1149.91
  4882.6 1147.25  4904.6 1146.92  4918.8 1145.66  4939.7 1142.15  4968.2 1138.68
  4996.8 1137.93  4997.6 1137.45  4998.1 1136.95  5008.6 1136.95  5009.1 1137.45
    5011 1138.94  5024.8 1141.03  5052.7 1146.75    5067 1148.38  5095.5 1150.93
  5103.2 1150.77  5124.1 1151.96  5195.4 1156.68  5244.8 1160.96  5265.6  1163.3
  5273.3 1164.75  5301.5  1166.9  5308.4 1168.25  5343.6 1170.51  5392.3 1175.13
#Mann= 3 ,-1 , 0
  4546.4     .05       0  4997.6     .05       0  5009.1     .05       0
Bank Sta=4997.6,5009.1
XS Rating Curve= 0 ,0
Exp/Cntr=0.3,0.1

Type RM Length L Ch R = 1 ,9622    ,447,447,447
BEGIN DESCRIPTION:
WILLOW BRANCH 13.0
END DESCRIPTION:
XS GIS Cut Line= 3
      2811192.38     10163475.67      2811596.04     10163397.54
      2811931.31     10163192.22
#Sta/Elev= 30
  4722.9 1161.87  4783.7 1159.12  4870.9 1154.58  4940.2  1146.3  4960.5 1142.07
  4991.1 1137.74  4995.5 1136.55    4996 1136.05    5007 1136.55  5026.3    1137
  5031.8 1139.46  5052.2 1143.29  5097.6 1144.95  5203.8  1148.5  5269.2  1152.1
  5297.8 1155.99  5304.5 1157.56  5325.8 1159.46  5341.2 1162.18  5356.4 1163.74
  5362.5 1165.41    5378 1167.42  5383.8 1169.28  5391.6 1170.12  5399.3 1172.01
  5414.7 1172.53  5449.4 1175.42  5472.7 1178.67  5515.3 1186.38  5527.2 1186.29
#Mann= 7 ,-1 , 0
  4722.9     .12       0  4783.7     .05       0  4995.5     .05       0
    5007     .05       0  5097.6     .12       0  5269.2     .05       0
  5449.4     .12       0
Bank Sta=4995.5,5007
XS Rating Curve= 0 ,0
Exp/Cntr=0.3,0.1

Type RM Length L Ch R = 1 ,9175    ,383,383,383
BEGIN DESCRIPTION:
WILLOW BRANCH 12.0
END DESCRIPTION:
XS GIS Cut Line= 3
      2811505.67     10164103.14      2811773.12     10163704.83
      2811970.85     10163364.01
#Sta/Elev= 30
  4607.8  1172.5  4610.8  1172.5  4636.4 1167.27  4651.3  1162.5  4657.4 1162.28
  4666.3 1159.56  4693.4 1154.47  4729.4 1151.54  4780.4  1148.6  4924.4 1141.85
  4933.1 1142.07  4969.2 1137.63  4975.4 1134.23  4984.5 1132.69    4985 1132.19
  4996.2 1132.69  5011.4 1135.37  5026.4 1135.88  5041.4  1137.7  5053.5 1140.89
  5078.3 1141.91  5259.6 1151.38  5300.4 1155.54  5355.5 1161.28  5398.7 1168.05
  5414.6 1169.07  5431.2 1170.24  5441.8 1170.57  5457.5 1172.61  5481.6 1173.78
#Mann= 8 ,-1 , 0
  4607.8     .05       0  4636.4     .12       0  4984.5     .05       0
  4996.2     .12       0  5078.3     .12       0  5300.4     .05       0
  5414.6     .12       0  5431.2     .05       0
Bank Sta=4984.5,4996.2
XS Rating Curve= 0 ,0
Exp/Cntr=0.3,0.1

Type RM Length L Ch R = 1 ,8792    ,352,352,352
BEGIN DESCRIPTION:
WILLOW BRANCH 11.0
END DESCRIPTION:
XS GIS Cut Line= 3
       2811635.1     10164350.67      2812069.18     10163970.69
      2812153.32     10163658.01
#Sta/Elev= 30
  4611.2 1165.57  4631.1 1164.74  4659.6 1161.63  4666.2 1162.48  4680.4 1161.34
    4688 1159.47  4730.7 1152.85  4758.3 1150.09  4886.4  1142.4  4935.7 1141.05
  4957.5 1139.75  4970.9 1137.31  4986.8 1131.49  4987.3 1130.99  4998.5 1131.49
  4999.3 1132.06  5027.8 1132.37  5049.6 1137.16  5091.4 1140.66  5141.7 1141.16
  5188.1  1143.5  5206.3 1145.25  5232.3 1146.01  5237.5 1146.95  5255.5 1146.93
    5307 1146.84  5381.7 1148.91  5439.1 1151.73  5496.3 1154.27  5511.9 1155.76
#Mann= 5 ,-1 , 0
  4611.2     .05       0  4986.8     .05       0  4998.5     .05       0
  5255.5     .12       0  5439.1     .05       0
Bank Sta=4986.8,4998.5
XS Rating Curve= 0 ,0
Exp/Cntr=0.3,0.1

Type RM Length L Ch R = 1 ,8440    ,369,369,369
BEGIN DESCRIPTION:
WILLOW BRANCH 10.0
END DESCRIPTION:
XS GIS Cut Line= 3
      2811898.15     10164821.98      2812237.56     10164227.75
       2812260.1     10163759.52
#Sta/Elev= 30
  4449.4 1158.07  4491.6 1156.48    4519 1154.41  4528.7 1154.64  4540.6 1153.59
  4599.6 1150.86  4701.8 1147.86  4717.7 1147.98  4878.9 1140.14  4908.7 1139.27
    4938 1139.59  4959.6 1138.95  4981.2 1132.04  4996.9 1129.99  4997.4 1129.49
  5008.1 1129.49  5008.6 1129.99  5034.4 1132.31  5046.9 1134.66  5061.8 1135.36
  5083.4 1137.45  5120.8 1139.17  5158.4 1139.03  5188.4 1139.82  5218.5 1139.03
  5268.7 1140.71  5398.7  1149.5  5478.8  1148.6  5530.1 1149.64  5602.5 1153.46
#Mann= 5 ,-1 , 0
  4449.4     .05       0  4996.9     .05       0  5008.6     .05       0
  5268.7     .12       0  5530.1     .05       0
Bank Sta=4996.9,5008.6
XS Rating Curve= 0 ,0
Exp/Cntr=0.3,0.1

Type RM Length L Ch R = 1 ,8071    ,425,425,425
BEGIN DESCRIPTION:
WILLOW BRANCH 9.0
END DESCRIPTION:
XS GIS Cut Line= 3
      2812431.98     10164986.09      2812515.31     10164348.06
      2812382.58     10163767.69
#Sta/Elev= 30
  4528.8 1153.78  4562.1 1153.09  4612.5 1150.45  4632.7 1148.34  4683.1  1145.2
  4743.6 1143.08  4834.4 1138.32  4907.4 1136.17  4965.5 1136.61  4975.5 1135.79
  4981.3 1132.79  4986.4 1132.73  4989.8 1127.61  4990.3 1127.11  5001.6 1127.61
  5046.1  1131.5  5076.4 1133.05  5157.1 1132.89  5172.2 1134.01  5218.4 1134.41
  5237.9 1135.42  5269.6 1137.37  5341.5 1137.42    5390 1138.67  5491.9 1140.46
  5593.7 1143.15  5612.9 1143.43  5669.7 1145.58  5695.5 1147.41  5767.6 1153.18
#Mann= 9 ,-1 , 0
  4528.8     .05       0  4989.8     .03       0  5001.6     .05       0
  5237.9     .12       0    5390     .05       0  5491.9     .12       0
  5593.7     .05       0  5612.9     .12       0  5695.5     .05       0
Bank Sta=4989.8,5001.6
XS Rating Curve= 0 ,0
Exp/Cntr=0.3,0.1

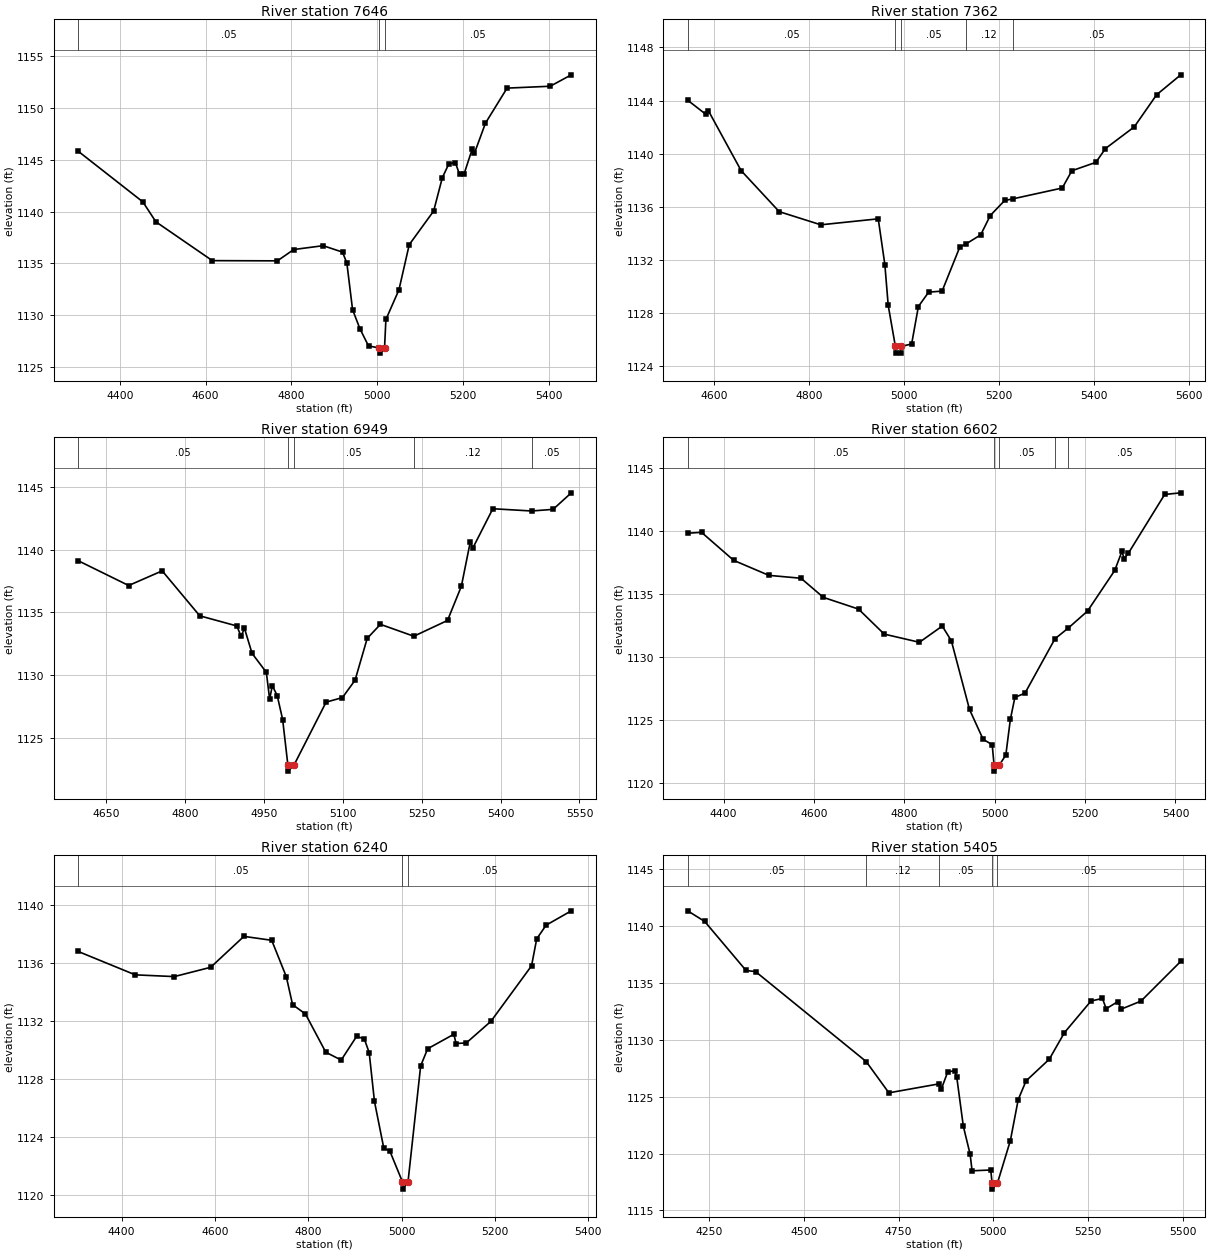
Type RM Length L Ch R = 1 ,7646    ,284,284,284
BEGIN DESCRIPTION:
WILLOW BRANCH 8.0
END DESCRIPTION:
XS GIS Cut Line= 3
      2812684.58     10165012.13      2812814.79     10164157.95
      2812843.43     10163874.14
#Sta/Elev= 30
  4303.2 1145.81  4453.9 1140.93  4484.3 1139.01  4615.8 1135.27  4767.5 1135.25
  4805.6 1136.34  4874.1 1136.71  4919.3 1136.09  4929.4 1135.03  4942.7 1130.55
  4959.7 1128.72  4979.9 1127.05  5005.4 1126.86  5005.9 1126.36  5017.2 1126.86
  5020.4  1129.6  5050.8 1132.46  5074.8 1136.81  5131.7 1140.05  5151.9 1143.26
  5167.2  1144.6  5182.2 1144.72  5192.2 1143.57  5202.3 1143.58  5221.6 1146.02
  5226.7 1145.61  5252.5 1148.52  5302.8 1151.89  5403.3 1152.07  5452.5 1153.17
#Mann= 3 ,-1 , 0
  4303.2     .05       0  5005.4     .03       0  5017.2     .05       0
Bank Sta=5005.4,5017.2
XS Rating Curve= 0 ,0
Exp/Cntr=0.3,0.1

Type RM Length L Ch R = 1 ,7362    ,413,413,413
BEGIN DESCRIPTION:
WILLOW BRANCH 7.0
END DESCRIPTION:
XS GIS Cut Line= 4
       2812817.4      10164965.2      2812846.04     10164618.89
      2813012.71     10164465.25      2813077.55     10164006.18
#Sta/Elev= 30
  4544.7 1144.03  4583.2 1142.96  4588.3 1143.24  4657.2 1138.73  4737.4 1135.64
    4825 1134.65  4945.8  1135.1  4959.7 1131.66  4966.8 1128.58  4981.9 1125.49
  4982.4 1124.99  4993.2 1124.99  4993.7 1125.49  5016.1 1125.68  5030.3  1128.5
  5051.9 1129.58  5080.2 1129.66  5117.5 1132.98    5130  1133.2  5161.4 1133.89
  5181.6 1135.35  5211.9 1136.48  5228.7  1136.6  5333.1 1137.42  5353.3 1138.72
  5403.8 1139.35    5424 1140.39  5484.6 1142.02  5531.7 1144.44  5582.5 1145.94
#Mann= 5 ,-1 , 0
  4544.7     .05       0  4981.9     .03       0  4993.7     .05       0
    5130     .12       0  5228.7     .05       0
Bank Sta=4981.9,4993.7
XS Rating Curve= 0 ,0
Exp/Cntr=0.3,0.1

Type RM Length L Ch R = 1 ,6949    ,347,347,347
BEGIN DESCRIPTION:
WILLOW BRANCH 6.0
END DESCRIPTION:
XS GIS Cut Line= 4
      2812986.69     10165168.34       2813192.4     10164907.95
      2813247.08     10164697.02      2813333.02     10164319.42
#Sta/Elev= 30
  4597.5 1139.12  4693.4 1137.14  4757.1 1138.31  4828.5 1134.72    4899 1133.91
    4907 1133.08  4913.4 1133.73  4927.9 1131.72    4955 1130.21  4961.3 1128.07
  4966.4 1129.14  4975.7 1128.35    4986 1126.44  4995.9 1122.82  4996.4 1122.32
  5007.8 1122.82  5068.6 1127.83  5099.6 1128.19  5123.6 1129.58  5146.7 1132.92
  5171.8 1134.04  5235.3 1133.09  5299.3 1134.35  5325.6 1137.08  5342.4 1140.59
  5347.5 1140.14  5385.4 1143.27  5459.1 1143.09  5499.9 1143.22  5534.5 1144.54
#Mann= 5 ,-1 , 0
  4597.5     .05       0  4995.9     .03       0  5007.8     .05       0
  5235.3     .12       0  5459.1     .05       0
Bank Sta=4995.9,5007.8
XS Rating Curve= 0 ,0
Exp/Cntr=0.3,0.1

Type RM Length L Ch R = 1 ,6602    ,362,362,362
BEGIN DESCRIPTION:
Mapping XS 0bf7026f
END DESCRIPTION:
XS GIS Cut Line= 3
      2813174.15     10165345.48      2813520.52     10164952.23
      2813572.55     10164387.66
#Sta/Elev= 30
  4320.7 1139.85  4351.4 1139.92  4422.6 1137.69  4500.4  1136.5  4571.5 1136.27
  4620.9 1134.75  4698.7 1133.82  4755.6 1131.83  4833.4 1131.18    4884 1132.47
  4904.1  1131.3  4944.3 1125.84  4974.4 1123.47  4994.5 1123.04  4998.6 1121.44
  4999.1 1120.94  5010.5 1121.44  5024.6 1122.21  5034.7 1125.06  5044.7  1126.8
  5067.1 1127.14  5133.4 1131.46  5163.1 1132.32  5205.4 1133.66  5265.6 1136.89
  5281.5  1138.4  5286.6 1137.83  5295.8 1138.26  5376.1 1142.93  5411.7 1143.06
#Mann= 5 ,-1 , 0
  4320.7     .05       0  4998.6     .03       0  5010.5     .05       0
  5133.4     .12       0  5163.1     .05       0
Bank Sta=4998.6,5010.5
XS Rating Curve= 0 ,0
Exp/Cntr=0.3,0.1

Type RM Length L Ch R = 1 ,6240    ,835,835,835
BEGIN DESCRIPTION:
WILLOW BRANCH 5.0
END DESCRIPTION:
XS GIS Cut Line= 3
      2813668.96     10165590.23      2813903.33      10164811.6
      2813929.37     10164569.44
#Sta/Elev= 30
  4307.1 1136.79  4429.4 1135.18    4513 1135.06    4591  1135.7  4662.2 1137.83
  4721.8 1137.56  4753.1 1135.05  4766.5 1133.13  4794.2 1132.48  4837.7 1129.85
  4870.7 1129.31  4903.7 1130.94  4920.2 1130.77  4930.7 1129.82    4942 1126.46
    4962 1123.24    4975 1123.04    5002 1120.92  5002.5 1120.42  5013.9 1120.92
    5041 1128.91    5056 1130.09  5112.2 1131.09  5116.8 1130.45  5138.8 1130.49
  5191.6 1131.98  5278.6  1135.8  5289.7 1137.66  5309.8  1138.6  5363.8 1139.59
#Mann= 3 ,-1 , 0
  4307.1     .05       0    5002     .03       0  5013.9     .05       0
Bank Sta=5002,5013.9
XS Rating Curve= 0 ,0
Exp/Cntr=0.3,0.1

Type RM Length L Ch R = 1 ,5405    ,318,318,318
BEGIN DESCRIPTION:
WILLOW BRANCH 4.0
END DESCRIPTION:
XS GIS Cut Line= 3
      2814421.55     10166056.42      2814655.94     10165160.56
       2814676.7     10164786.85
#Sta/Elev= 30
  4193.7 1141.32  4238.5 1140.39  4347.6 1136.08  4372.8 1135.98  4664.4 1128.08
  4724.3 1125.33    4857 1126.12  4862.9 1125.69  4879.3 1127.15  4898.1 1127.29
  4903.3 1126.71  4920.7 1122.38  4938.6 1119.93  4943.7 1118.48    4993 1118.55
  4996.5 1117.37    4997 1116.87  5010.3 1117.37  5044.7 1121.14  5065.4 1124.74
  5086.1 1126.38  5147.2 1128.28  5187.3 1130.62  5257.4  1133.4  5287.4 1133.62
  5297.4 1132.72  5327.5 1133.33  5337.5 1132.69  5389.1 1133.39    5494 1136.88
#Mann= 5 ,-1 , 0
  4193.7     .05       0  4664.4     .12       0    4857     .05       0
  4996.5     .03       0  5010.3     .05       0
Bank Sta=4996.5,5010.3
XS Rating Curve= 0 ,0
Exp/Cntr=0.3,0.1

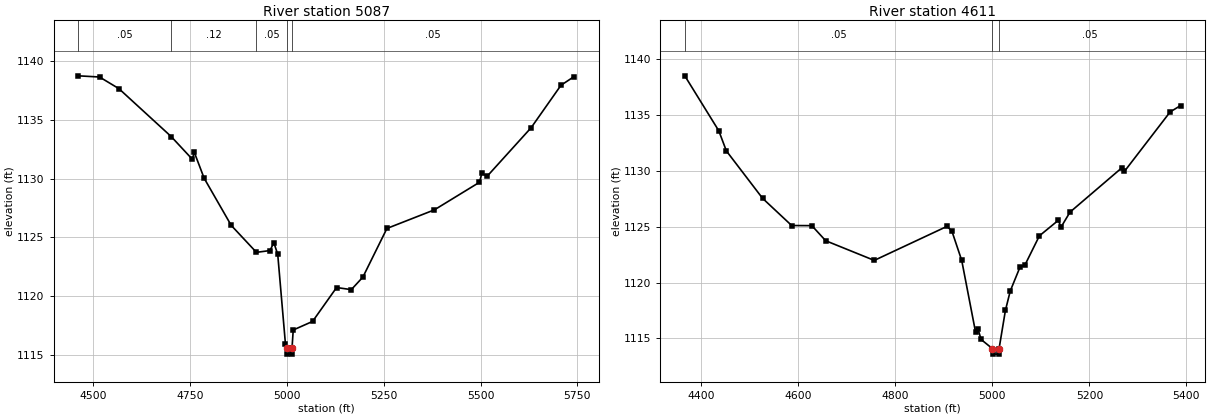
Type RM Length L Ch R = 1 ,5087    ,476,476,476
BEGIN DESCRIPTION:
WILLOW BRANCH 3.0
END DESCRIPTION:
XS GIS Cut Line= 3
       2814882.5     10165967.87      2814903.33     10165207.43
      2814861.67     10164689.23
#Sta/Elev= 30
  4461.1 1138.73  4515.9 1138.63  4565.9 1137.64  4700.9 1133.57  4755.5 1131.64
  4760.5 1132.24    4786 1130.03    4856 1126.02  4921.1 1123.73    4956 1123.88
  4966.1 1124.55  4976.1 1123.56  4996.1 1115.91  4999.1 1115.58  4999.6 1115.08
  5012.5 1115.08    5013 1115.58  5016.1 1117.13  5066.1 1117.86  5128.1 1120.74
  5166.1 1120.56  5196.1 1121.63  5258.1 1125.76  5380.7 1127.34    5497 1129.68
  5503.2 1130.43  5517.1  1130.2  5630.8 1134.33  5707.7 1137.93  5741.7 1138.67
#Mann= 5 ,-1 , 0
  4461.1     .05       0  4700.9     .12       0  4921.1     .05       0
  4999.1     .03       0    5013     .05       0
Bank Sta=4999.1,5013
XS Rating Curve= 0 ,0
Exp/Cntr=0.3,0.1

Type RM Length L Ch R = 1 ,4611    ,370,370,370
BEGIN DESCRIPTION:
WILLOW BRANCH 2.0
END DESCRIPTION:
XS GIS Cut Line= 3
      2815305.68     10165853.11      2815262.71     10165113.68
      2815155.67     10164853.09
#Sta/Elev= 30
  4365.7 1138.51  4435.8 1133.59  4451.4 1131.79    4526 1127.55  4586.1 1125.11
  4627.7  1125.1  4656.2 1123.75  4756.4 1121.99  4906.6 1125.04  4916.6 1124.59
  4936.7 1121.99  4965.3 1115.56  4970.3 1115.84  4976.7 1114.91  4999.8  1114.1
  5000.3  1113.6  5013.3  1113.6  5013.8  1114.1  5026.8 1117.51  5036.8 1119.25
  5056.9 1121.39  5066.9 1121.56  5096.9 1124.19    5136 1125.58  5141.4 1124.96
    5160 1126.31  5266.7 1130.27  5272.1 1129.95  5366.5 1135.28  5388.1 1135.85
#Mann= 3 ,-1 , 0
  4365.7     .05       0  4999.8     .03       0  5013.8     .05       0
Bank Sta=4999.8,5013.8
XS Rating Curve= 0 ,0
Exp/Cntr=0.3,0.1