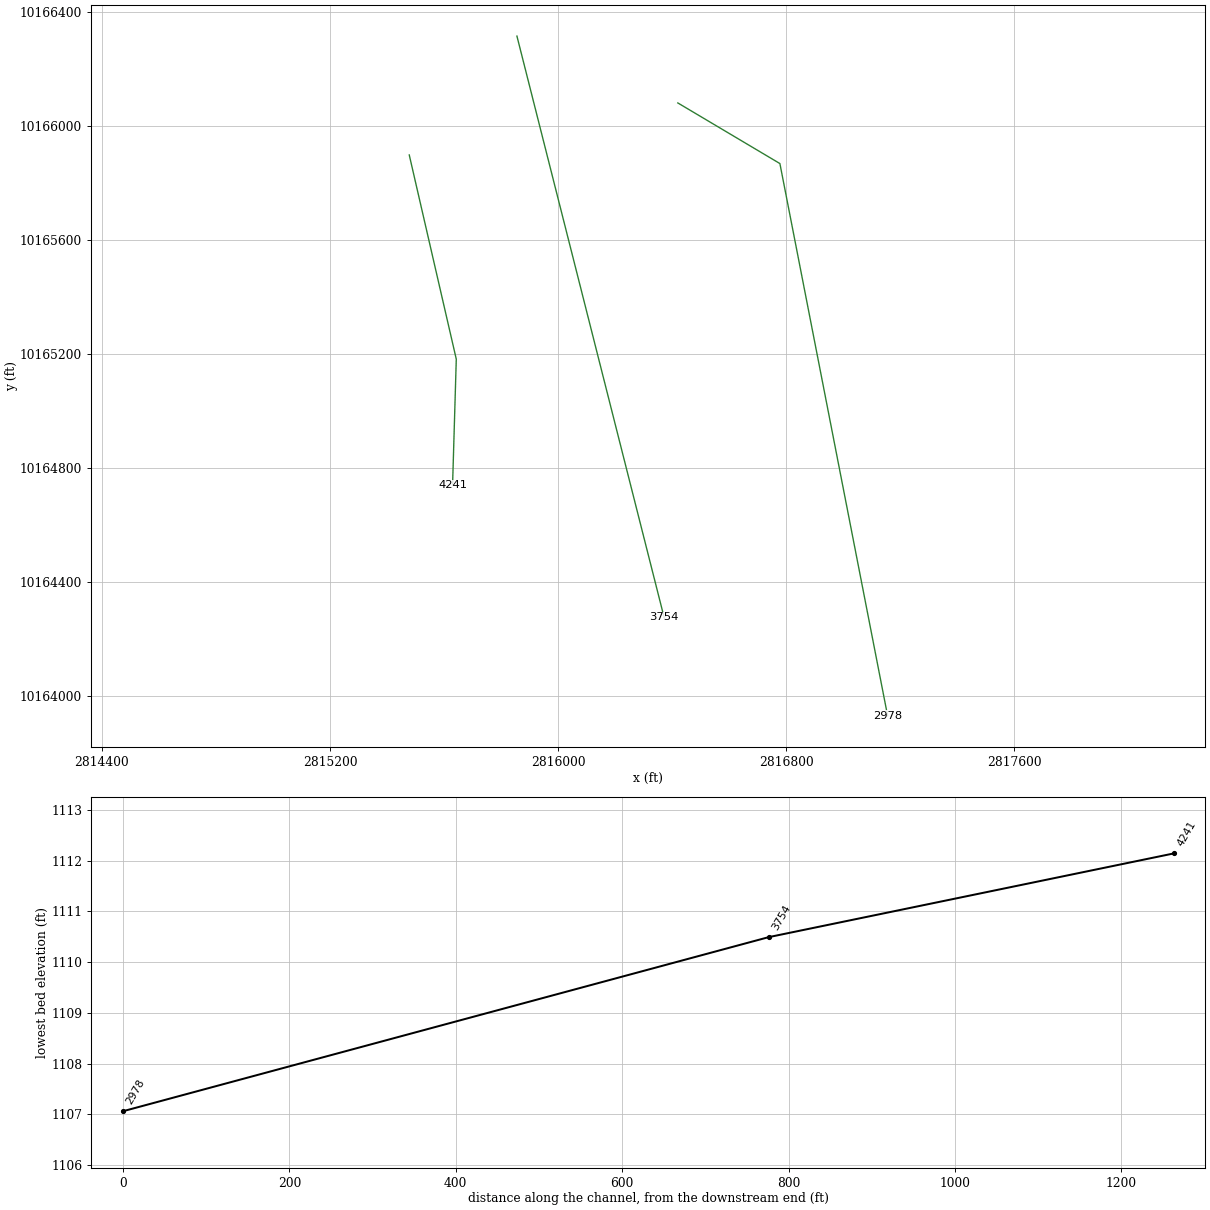
HEC-RAS study WILLOW BRANCH.prj: WILLOW BRANCH Base Level Engineering

--- WILLOW BRANCH.g01 (geometry) --- (continued)

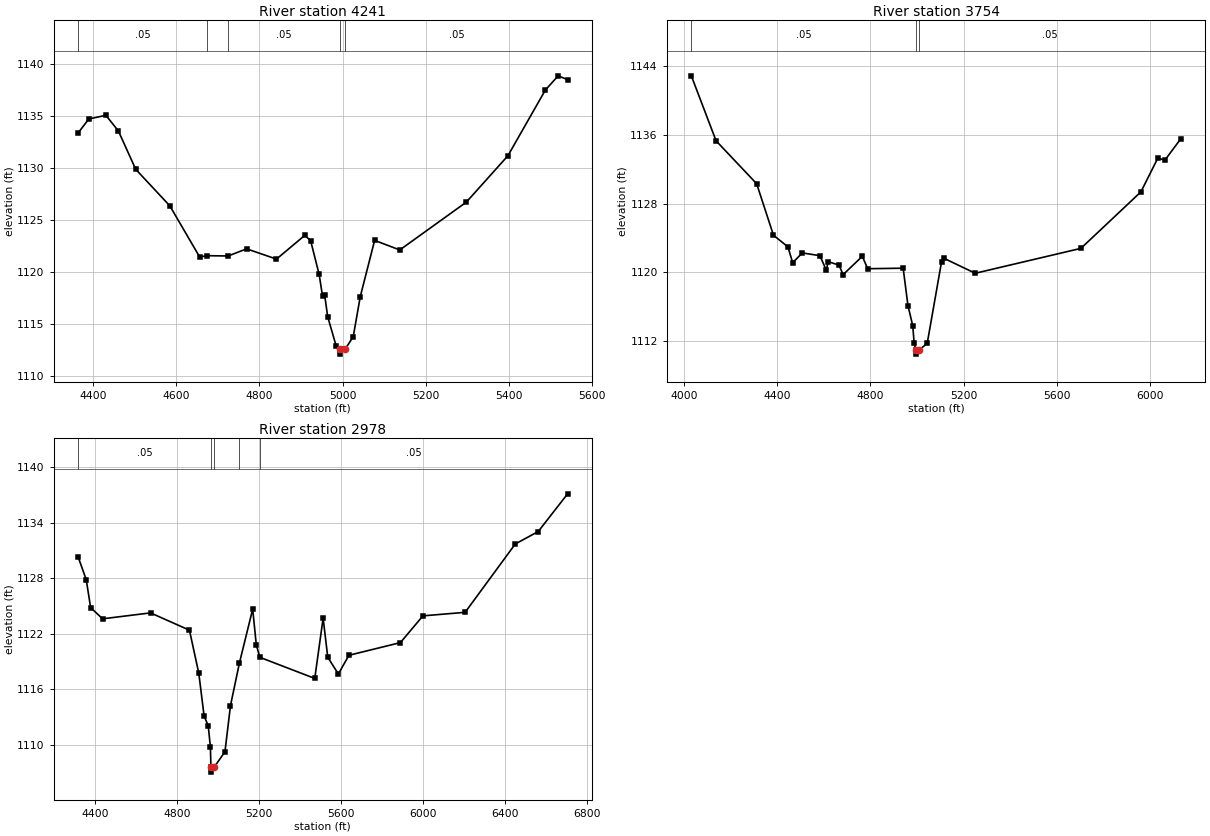
Type RM Length L Ch R = 1 ,4241    ,487,487,487
BEGIN DESCRIPTION:
Mapping XS ade73795
END DESCRIPTION:
XS GIS Cut Line= 3
      2815477.99     10165898.37      2815642.92     10165182.26
      2815629.89      10164739.5
#Sta/Elev= 30
  4363.5  1133.4  4389.4 1134.76  4430.5 1135.11  4460.4 1133.62  4502.3 1129.92
  4584.4  1126.4  4656.2 1121.48  4673.1 1121.61  4724.6 1121.58  4769.1 1122.27
  4840.9 1121.28  4908.9 1123.56    4923 1123.06  4943.6  1119.8  4951.7 1117.71
  4956.8 1117.82  4964.1 1115.74  4984.6 1112.91  4992.6 1112.64  4993.1 1112.14
  5006.6 1112.64  5025.6 1113.83  5042.4 1117.66    5077 1123.08  5137.5 1122.16
  5297.6 1126.76  5397.6 1131.22  5487.7 1137.54  5518.5 1138.91  5541.3 1138.54
#Mann= 5 ,-1 , 0
  4363.5     .05       0  4673.1     .12       0  4724.6     .05       0
  4992.6     .03       0  5006.6     .05       0
Bank Sta=4992.6,5006.6
XS Rating Curve= 0 ,0
Exp/Cntr=0.3,0.1

Type RM Length L Ch R = 1 ,3754    ,776,776,776
BEGIN DESCRIPTION:
Mapping XS 54160a62
END DESCRIPTION:
XS GIS Cut Line= 2
      2815855.58      10166315.1      2816371.71     10164276.62
#Sta/Elev= 30
  4030.5 1142.91  4136.8 1135.34  4311.1 1130.34  4383.3 1124.34  4445.2 1122.99
  4465.8 1121.14  4507.1 1122.28  4582.7 1121.96  4610.2 1120.27  4618.5 1121.26
  4664.7 1120.86  4682.4 1119.75    4765 1121.89  4787.7 1120.44  4940.3  1120.5
  4960.9 1116.14  4981.6 1113.78  4987.5 1111.75  4995.2 1110.99  4995.7 1110.49
  5009.3 1110.99  5043.5 1111.73  5105.4 1121.28  5115.7 1121.65  5249.8 1119.91
  5703.7 1122.81  5961.3 1129.39  6033.8 1133.31  6064.7  1133.1  6133.3  1135.6
#Mann= 3 ,-1 , 0
  4030.5     .05       0  4995.2     .03       0  5009.3     .05       0
Bank Sta=4995.2,5009.3
XS Rating Curve= 0 ,0
Exp/Cntr=0.3,0.1

Type RM Length L Ch R = 1 ,2978    ,0,0,0
BEGIN DESCRIPTION:
WILLOW BRANCH 1.0
END DESCRIPTION:
XS GIS Cut Line= 3
      2816419.79     10166080.72      2816777.67     10165868.15
      2817155.28     10163932.38
#Sta/Elev= 30
  4315.8 1130.34  4355.9 1127.84  4377.3 1124.83  4435.8 1123.62  4669.6 1124.26
  4859.4 1122.39  4904.9 1117.75  4930.8 1113.13  4951.1 1112.06  4961.6 1109.76
  4964.3 1107.56  4964.8 1107.06  4978.8 1107.56  5032.6 1109.26  5059.6 1114.25
  5103.4 1118.87  5167.9 1124.67  5185.5 1120.81  5202.8 1119.46  5470.7 1117.18
  5511.5 1123.69  5534.1 1119.47  5585.7 1117.66  5637.3 1119.68  5888.5 1121.05
  5998.4 1123.94  6204.3 1124.32  6448.8  1131.7  6560.9 1133.05  6704.3 1137.12
#Mann= 5 ,-1 , 0
  4315.8     .05       0  4964.3     .03       0  4978.8     .05       0
  5103.4     .12       0  5202.8     .05       0
Bank Sta=4964.3,4978.8
XS Rating Curve= 0 ,0
Exp/Cntr=0.3,0.1

Chan Stop Cuts=-1
Use User Specified Reach Order=0
Composite Channel Slope=5