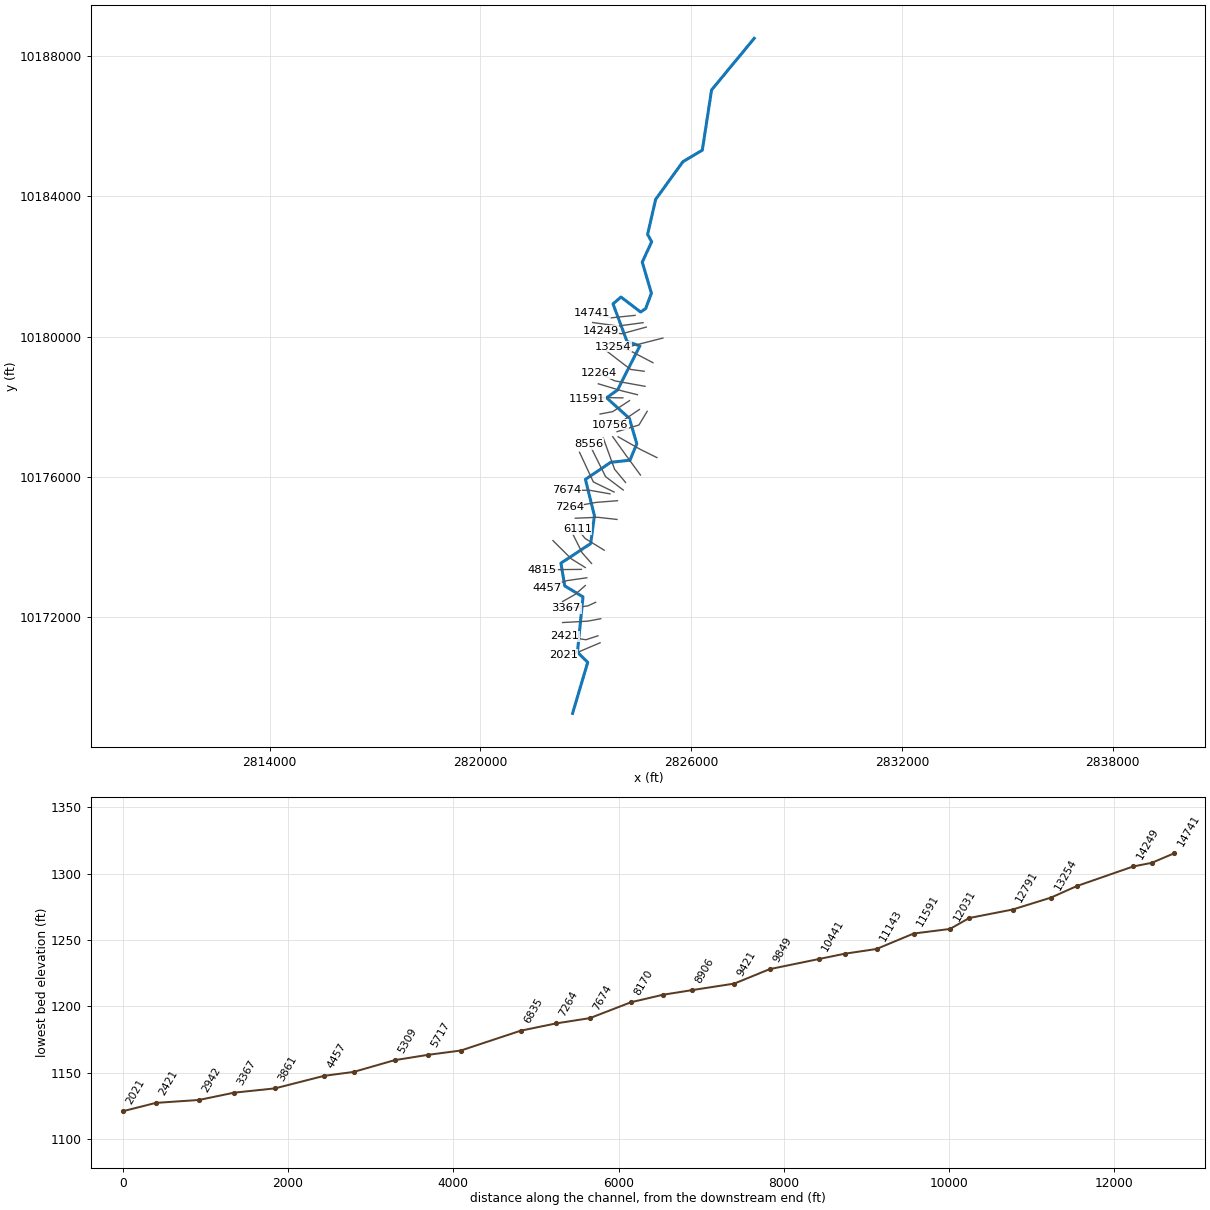
--- SILVER CREEK.prj (project) ---

Proj Title=SILVER CREEK Base Level Engineering
Current Plan=p01
Default Exp/Contr=0.3,0.1
English Units
Geom File=g01
Flow File=f01
Plan File=p01
Y Axis Title=Elevation
X Axis Title(PF)=Main Channel Distance
X Axis Title(XS)=Station
BEGIN DESCRIPTION:
SILVER CREEK
END DESCRIPTION:
DSS Export Rating Curves= 0
DSS Export Rating Curve Sorted= 0
DSS Export Volume Flow Curves= 0
DXF OffsetX= 0
DXF OffsetY= 0
DXF ScaleX= 1
DXF ScaleY= 10

--- SILVER CREEK.p01 (plan) ---

Plan Title=Multiple Run
Short Identifier=Multiple
Geom File=g01
Flow File=f01
Subcritical Flow
K Sum by GR= 0
Std Step Tol= 0.01
Critical Tol= 0.01
Num of Std Step Trials= 20
Max Error Tol= 0.3
Flow Tol Ratio= 0.001
Split Flow NTrial= 30
Split Flow Tol= 0.02
Split Flow Ratio= 0.02
Log Output Level= 0
Friction Slope Method= 1
Unsteady Friction Slope Method= 2
Unsteady Bridges Friction Slope Method= 1
Parabolic Critical Depth
Global Vel Dist=  1 , 1 , 1
Global Log Level= 0
CheckData=True
Encroach Param= -1, 0, 0, 0
BEGIN DESCRIPTION:
Multiple Run
END DESCRIPTION:

--- SILVER CREEK.f01 (steady flow) ---

Flow Title=Multiple
Number of Profiles=7
Profile Names=10-year,25-year,50-year,1pct_min,100-year,1pct_plu,500-year
River Rch & RM= SILVER CREEK,Reach-1,14741
     875    1486    3250    2450    4701    9021    6849
River Rch & RM= SILVER CREEK,Reach-1,12264
    1332    2342    4970    3496    7289   15199   10636
Boundary for River Rch & Prof#=SILVER CREEK,Reach-1,1
Up Type=0
Dn Type=3
Dn Slope=0.005
Boundary for River Rch & Prof#=SILVER CREEK,Reach-1,2
Up Type=0
Dn Type=3
Dn Slope=0.005
Boundary for River Rch & Prof#=SILVER CREEK,Reach-1,3
Up Type=0
Dn Type=3
Dn Slope=0.005
Boundary for River Rch & Prof#=SILVER CREEK,Reach-1,4
Up Type=0
Dn Type=3
Dn Slope=0.005
Boundary for River Rch & Prof#=SILVER CREEK,Reach-1,5
Up Type=0
Dn Type=3
Dn Slope=0.005
Boundary for River Rch & Prof#=SILVER CREEK,Reach-1,6
Up Type=0
Dn Type=3
Dn Slope=0.005
Boundary for River Rch & Prof#=SILVER CREEK,Reach-1,7
Up Type=0
Dn Type=3
Dn Slope=0.005

--- SILVER CREEK.g01 (geometry) ---

Geom Title=Existing Conditions
Program Version=4.10

River Reach=SILVER CREEK    ,Reach-1
Reach XY= 30
        2827796.       10188499.      2826581.25       10187028.
       2826317.5       10185312.      2825765.25       10184984.
      2824988.75       10183910.       2824759.5       10182912.
      2824875.25       10182701.        2824607.       10182121.
      2824868.25       10181235.       2824704.5       10180798.
        2824560.       10180700.       2824001.5       10181126.
      2823774.25       10180931.      2824174.25       10179858.
      2824540.25       10179735.       2823902.5       10178477.
      2823591.75       10178255.      2824240.75       10177668.
       2824451.5       10176945.       2824257.5       10176476.
        2823709.       10176416.        2822988.       10175929.
        2823245.       10174892.      2823138.75       10174100.
       2822291.5       10173542.        2822399.       10172895.
       2822919.5       10172581.       2822761.5       10171006.
      2823054.25       10170716.       2822622.5       10169261.

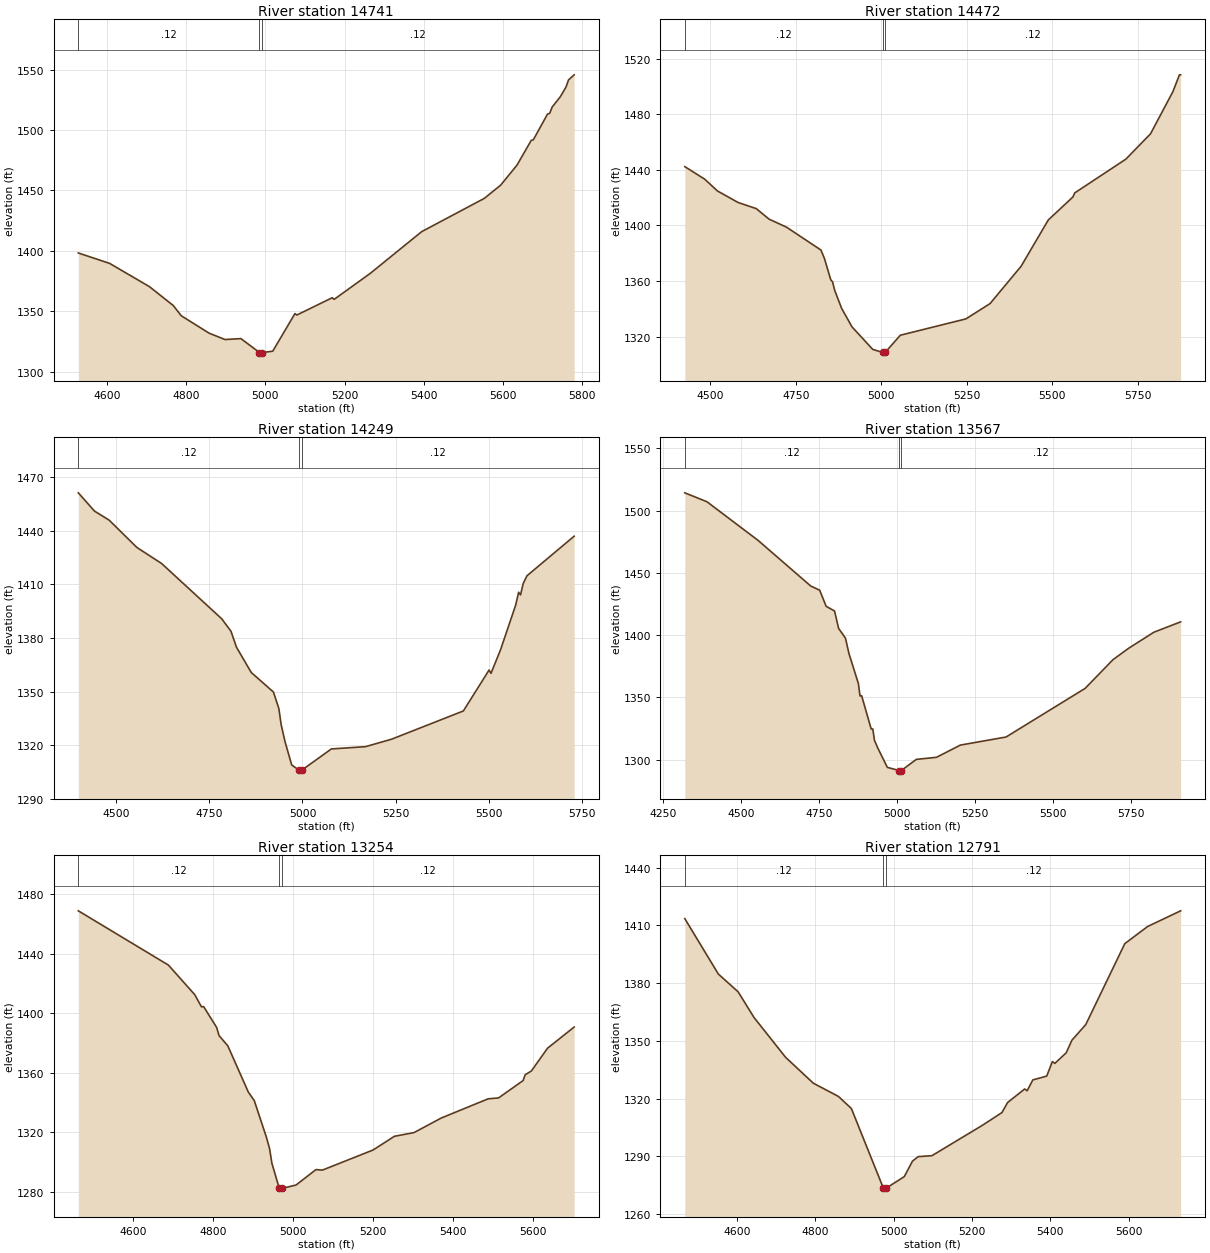
Type RM Length L Ch R = 1 ,14741   ,269,269,269
BEGIN DESCRIPTION:
SILVER CREEK 33.0
END DESCRIPTION:
XS GIS Cut Line= 3
      2824404.52     10180604.05      2823727.42     10180534.61
      2823171.87      10180673.5
#Sta/Elev= 30
  4527.1 1398.24  4606.3 1389.62  4706.9 1370.36  4767.2 1354.72  4787.3 1346.28
  4857.7 1331.85  4897.9 1326.59  4938.1 1327.36    4985 1315.84  4985.5 1315.34
  4991.7 1315.84  5018.5 1316.93  5074.6 1348.05  5079.6  1346.9  5168.8 1361.19
  5173.9 1359.87  5264.8 1381.31  5395.1 1415.93  5553.4 1443.47  5594.7 1454.42
  5635.9 1470.98    5672 1491.53  5677.1 1491.88  5713.2 1513.31  5718.4 1513.78
  5724.9  1519.1  5745.5 1527.64  5759.6 1535.48  5766.2 1541.53  5780.4 1545.73
#Mann= 3 ,-1 , 0
  4527.1     .12       0    4985     .07       0  4991.7     .12       0
Bank Sta=4985,4991.7
XS Rating Curve= 0 ,0
Exp/Cntr=0.3,0.1

Type RM Length L Ch R = 1 ,14472   ,223,223,223
BEGIN DESCRIPTION:
SILVER CREEK 32.0
END DESCRIPTION:
XS GIS Cut Line= 3
       2824630.2     10180395.72      2823922.74     10180300.23
      2823193.61     10180400.05
#Sta/Elev= 30
  4425.3 1442.34  4483.8 1433.25  4520.7 1424.84  4581.2 1416.53  4634.2 1412.14
    4672 1404.52  4722.5 1398.83  4823.4 1382.34  4833.5 1376.37  4852.3 1360.81
  4857.3 1359.52  4863.8 1353.21  4883.9 1340.39  4914.2 1327.11  4974.8  1310.9
  5004.4 1308.71  5004.9 1308.21  5011.2 1308.71  5055.5 1321.08  5247.2 1332.82
  5317.9 1343.84  5408.7 1370.69  5488.3 1404.01  5560.1 1420.49  5565.5 1423.43
  5714.9 1447.68  5787.1 1465.93  5852.8 1496.37  5871.6 1508.34  5875.1 1508.34
#Mann= 3 ,-1 , 0
  4425.3     .12       0  5004.4     .07       0  5011.2     .12       0
Bank Sta=5004.4,5011.2
XS Rating Curve= 0 ,0
Exp/Cntr=0.3,0.1

Type RM Length L Ch R = 1 ,14249   ,682,682,682
BEGIN DESCRIPTION:
SILVER CREEK 31.0
END DESCRIPTION:
XS GIS Cut Line= 3
      2824721.31     10180269.84      2824022.56     10180078.88
      2823419.96     10180156.91
#Sta/Elev= 30
  4397.9 1461.29  4441.2 1451.09  4480.9 1445.97  4555.1 1430.72  4621.4 1421.76
    4783 1390.79    4808  1383.8  4822.7 1374.89  4862.4 1360.72  4922.1 1349.76
  4936.6  1340.5  4942.8 1331.53  4953.2 1321.97  4971.1 1308.94  4991.2 1305.99
  4991.7 1305.49    4998 1305.99  5077.6 1317.91  5169.5 1319.19  5240.1 1323.41
  5432.3 1339.18  5501.4 1362.09  5506.5 1360.22  5532.5 1373.62  5572.9  1398.5
  5580.7  1405.6  5585.8 1404.14    5593  1410.5  5603.1 1414.85  5729.9 1437.01
#Mann= 3 ,-1 , 0
  4397.9     .12       0  4991.2     .07       0    4998     .12       0
Bank Sta=4991.2,4998
XS Rating Curve= 0 ,0
Exp/Cntr=0.3,0.1

Type RM Length L Ch R = 1 ,13567   ,313,313,313
BEGIN DESCRIPTION:
SILVER CREEK 30.0
END DESCRIPTION:
XS GIS Cut Line= 4
      2825194.44     10179957.35      2824713.08     10179834.21
      2824261.28     10179718.64      2823640.69     10179796.75
#Sta/Elev= 30
  4320.1 1514.21  4391.1 1507.05  4555.1 1475.98  4723.5  1439.4  4752.3    1436
    4773 1423.08    4800 1419.31    4813 1405.29  4834.9 1397.52    4846 1385.26
  4876.2 1361.13  4881.6 1351.06  4886.8 1351.26  4917.3 1324.57  4922.5 1324.58
  4927.8 1315.52  4938.1 1309.51  4969.1 1293.73  5006.9 1291.22  5007.4 1290.72
  5013.8 1291.22    5062 1300.14  5126.6 1301.82    5203 1311.62  5349.4 1318.11
  5602.9 1357.18  5692.1 1380.23  5742.5 1389.42  5823.1 1402.27  5908.8 1410.58
#Mann= 3 ,-1 , 0
  4320.1     .12       0  5006.9     .07       0  5013.8     .12       0
Bank Sta=5006.9,5013.8
XS Rating Curve= 0 ,0
Exp/Cntr=0.3,0.1

Type RM Length L Ch R = 1 ,13254   ,463,463,463
BEGIN DESCRIPTION:
SILVER CREEK 29.0
END DESCRIPTION:
XS GIS Cut Line= 3
      2824912.29     10179254.24      2824226.55     10179614.47
      2823770.86     10179714.29
#Sta/Elev= 30
  4462.1 1468.65  4687.6 1432.26  4753.8 1412.33  4770.2 1404.29  4775.8 1404.39
  4808.4 1390.41  4814.3    1385  4836.3 1378.09  4887.5 1347.16  4902.5 1341.36
  4932.7 1316.97  4940.9 1309.02  4946.6 1299.38  4965.1  1282.5  4965.6    1282
  4972.1  1282.5  5007.1 1284.75  5056.9  1295.1  5073.2 1294.77  5199.8 1308.23
  5253.3 1317.44  5302.3 1319.91  5370.7  1329.7  5487.9 1342.56    5514 1343.16
  5575.4 1354.81  5580.7 1358.74  5595.9 1361.18  5636.8 1376.57  5703.2 1390.69
#Mann= 3 ,-1 , 0
  4462.1     .12       0  4965.1     .07       0  4972.1     .12       0
Bank Sta=4965.1,4972.1
XS Rating Curve= 0 ,0
Exp/Cntr=0.3,0.1

Type RM Length L Ch R = 1 ,12791   ,527,527,527
BEGIN DESCRIPTION:
SILVER CREEK 28.0
END DESCRIPTION:
XS GIS Cut Line= 3
       2824660.6     10179011.17       2824274.3     10179063.25
      2823580.27     10179596.79
#Sta/Elev= 30
  4467.1 1413.54  4552.8 1384.73  4603.2 1375.52  4643.6 1362.22  4724.3  1341.5
    4795 1328.06  4859.2 1321.16  4892.2 1314.88  4973.8 1273.52  4974.3 1273.02
  4980.9 1273.52  5027.2 1279.52    5048 1287.54  5062.5 1289.89  5097.8  1290.4
  5226.5 1306.18  5276.4 1312.79  5290.9 1318.03  5334.4 1325.04  5340.7 1324.13
  5355.2 1329.76  5390.6 1331.73  5405.1 1339.29  5411.4 1338.34  5440.4 1343.85
  5454.9 1350.38  5490.2 1358.48  5589.9 1400.56    5648 1409.43  5732.3 1417.59
#Mann= 3 ,-1 , 0
  4467.1     .12       0  4973.8     .07       0  4980.9     .12       0
Bank Sta=4973.8,4980.9
XS Rating Curve= 0 ,0
Exp/Cntr=0.3,0.1

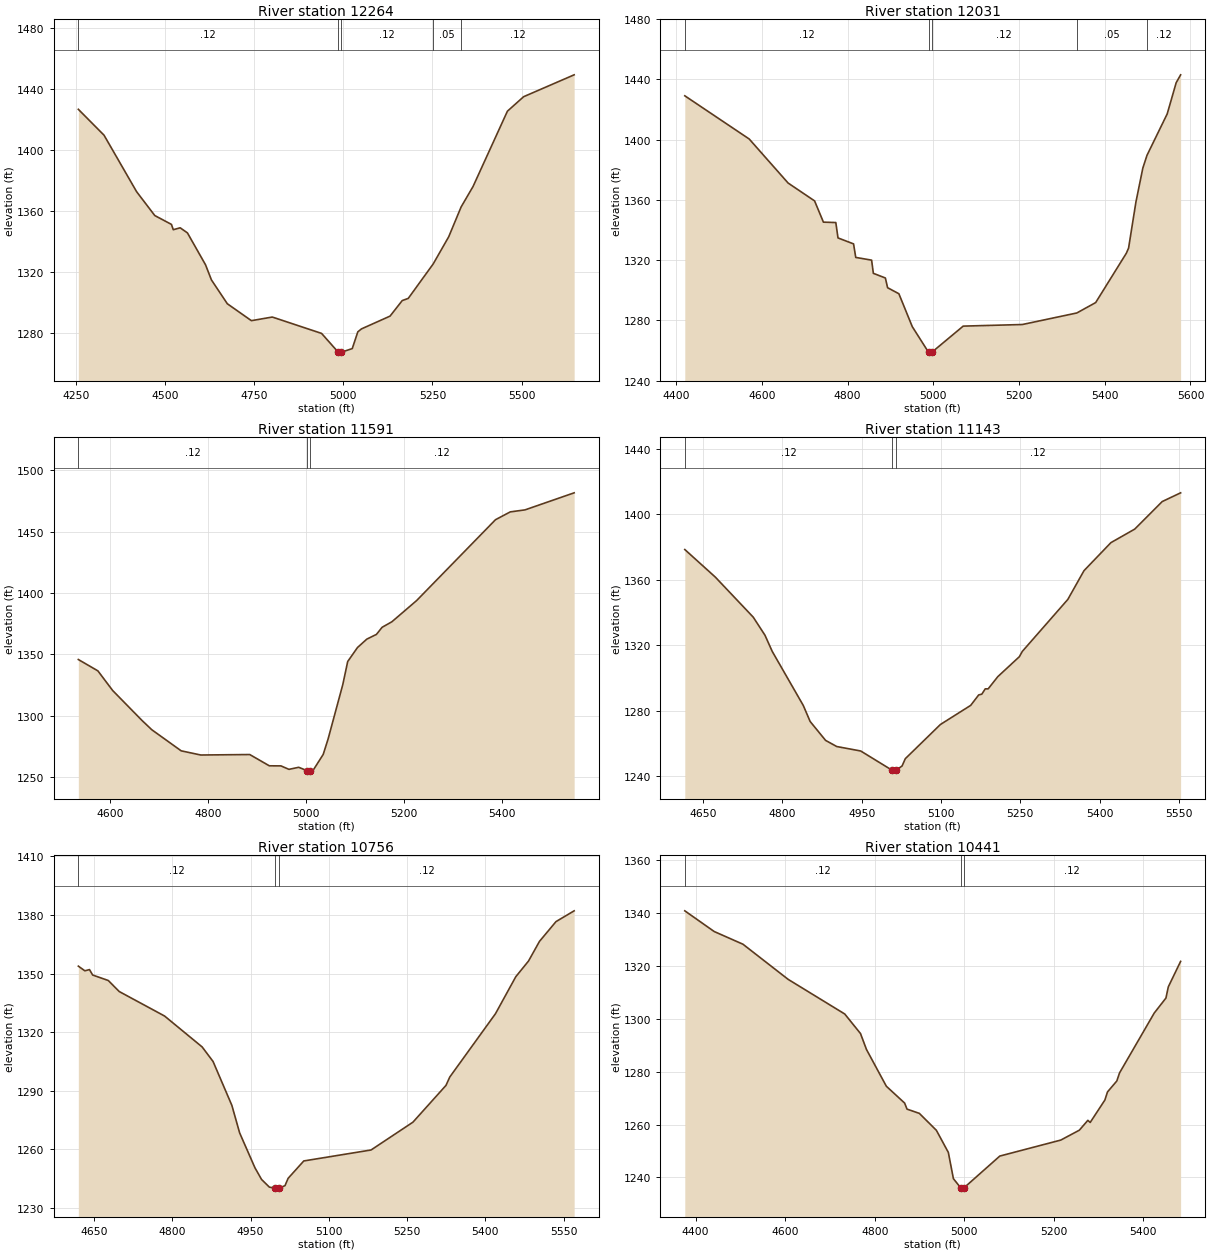
Type RM Length L Ch R = 1 ,12264   ,233,233,233
BEGIN DESCRIPTION:
SILVER CREEK 27.0
END DESCRIPTION:
XS GIS Cut Line= 3
      2824686.61     10178581.49      2823822.91     10178737.73
      2823360.65     10178958.06
#Sta/Elev= 30
  4257.4  1426.5  4329.5  1409.5  4420.9 1372.42  4471.7 1356.82  4518.4 1351.01
  4523.5 1347.53  4542.9 1348.78  4563.2 1345.45    4614  1324.5  4630.5  1314.6
    4675 1298.98  4742.5 1287.88  4801.1 1290.25  4939.2 1279.53  4986.4 1267.09
  4986.9 1266.59  4993.6 1267.09  5025.2 1269.56  5040.8 1280.54    5051 1282.48
  5131.2 1290.87  5165.3 1301.06  5182.2 1302.49  5252.2 1325.12  5295.7 1342.95
  5330.3 1362.43  5363.8 1375.87  5460.1 1425.25  5505.5 1434.75  5647.2 1449.11
#Mann= 5 ,-1 , 0
  4257.4     .12       0  4986.4     .07       0  4993.6     .12       0
  5252.2     .05       0  5330.3     .12       0
Bank Sta=4986.4,4993.6
XS Rating Curve= 0 ,0
Exp/Cntr=0.3,0.1

Type RM Length L Ch R = 1 ,12031   ,440,440,440
BEGIN DESCRIPTION:
SILVER CREEK 26.0
END DESCRIPTION:
XS GIS Cut Line= 3
      2824469.65     10178342.76       2824048.6     10178446.93
      2823355.67     10178653.12
#Sta/Elev= 30
  4420.4 1429.16  4570.7 1400.47  4661.4 1371.25  4723.2 1359.39  4743.8 1345.29
  4772.7 1345.02  4777.8 1334.81  4814.1 1330.86  4819.2 1321.87  4856.2 1320.07
  4860.3 1311.31  4888.3 1308.22  4893.5 1301.76  4919.8 1297.78  4951.1 1275.91
  4989.2 1258.84  4989.7 1258.34  4996.4 1258.84  5069.9 1276.27  5207.8 1277.33
    5335    1285  5378.9 1291.89  5450.5 1324.66  5455.7 1328.08  5472.8  1358.6
  5488.9 1381.13  5498.6 1389.62  5545.8 1417.15  5566.7 1437.82  5577.1 1443.08
#Mann= 5 ,-1 , 0
  4420.4     .12       0  4989.2     .07       0  4996.4     .12       0
    5335     .05       0  5498.6     .12       0
Bank Sta=4989.2,4996.4
XS Rating Curve= 0 ,0
Exp/Cntr=0.3,0.1

Type RM Length L Ch R = 1 ,11591   ,448,448,448
BEGIN DESCRIPTION:
SILVER CREEK 25.0
END DESCRIPTION:
XS GIS Cut Line= 3
      2824055.67     10178253.11      2823462.67      10178260.3
      2823046.04     10178212.56
#Sta/Elev= 30
  4535.6 1345.81  4575.6 1336.55  4605.6 1320.61  4665.6 1296.17  4685.6  1288.6
  4745.6 1271.42  4785.6 1268.01  4885.6 1268.39  4925.6 1259.21  4949.3 1259.15
  4965.6 1256.33  4985.6 1257.99    5002 1255.38  5002.5 1254.88  5009.3 1255.38
  5015.6 1255.94  5035.6 1268.49  5045.6 1281.09  5075.6  1325.4  5085.6 1344.17
  5105.6 1355.57  5124.6 1362.41  5144.3 1366.28  5155.8 1372.03  5175.9 1376.58
  5226.3 1393.82  5387.3 1459.68  5417.5 1466.07  5447.7 1467.72    5548 1481.61
#Mann= 3 ,-1 , 0
  4535.6     .12       0    5002     .07       0  5009.3     .12       0
Bank Sta=5002,5009.3
XS Rating Curve= 0 ,0
Exp/Cntr=0.3,0.1

Type RM Length L Ch R = 1 ,11143   ,387,387,387
BEGIN DESCRIPTION:
SILVER CREEK 24.0
END DESCRIPTION:
XS GIS Cut Line= 3
      2824243.95     10178173.52      2823766.49       10177861.
      2823406.27     10177791.56
#Sta/Elev= 30
  4615.6 1378.46  4673.3 1361.64    4745 1337.19  4767.2 1326.17  4780.9 1316.31
  4839.6 1283.33  4852.6 1273.54  4881.8    1262  4902.9 1258.25  4948.2 1255.53
  5007.8 1243.74  5008.3 1243.24  5015.1 1243.74  5026.5 1246.41  5032.5 1250.82
  5098.9 1271.69  5156.2 1283.37  5171.3 1289.74  5177.2  1290.2  5183.7 1293.45
  5189.2 1293.45  5207.4 1300.88  5248.2 1313.07  5253.8 1316.31  5339.8    1348
  5370.4 1365.56  5421.3 1382.66  5466.4 1390.94  5518.3 1407.73  5553.1 1413.06
#Mann= 3 ,-1 , 0
  4615.6     .12       0  5007.8     .07       0  5015.1     .12       0
Bank Sta=5007.8,5015.1
XS Rating Curve= 0 ,0
Exp/Cntr=0.3,0.1

Type RM Length L Ch R = 1 ,10756   ,315,315,315
BEGIN DESCRIPTION:
SILVER CREEK 23.0
END DESCRIPTION:
XS GIS Cut Line= 3
      2824526.01     10177921.74      2824057.28     10177604.92
      2823692.66     10177483.38
#Sta/Elev= 30
    4620 1353.77  4632.5 1351.38  4641.4    1352  4647.5 1349.22  4677.4 1346.42
  4698.4 1340.77  4785.3 1328.23  4857.2 1312.43  4878.2 1304.96  4914.2 1282.52
  4929.1 1268.43  4958.4 1250.59  4971.1 1244.59  4986.1 1240.66  4997.3 1240.14
  4997.8 1239.64  5004.7 1240.14    5016 1241.42    5022 1245.16    5052 1254.06
  5180.9 1259.67  5261.2 1273.91  5324.5 1292.74  5331.8 1297.03  5419.3 1329.41
  5458.3 1348.37  5482.6 1356.36  5503.7 1366.46  5535.3 1376.56  5570.1 1382.08
#Mann= 3 ,-1 , 0
    4620     .12       0  4997.3     .07       0  5004.7     .12       0
Bank Sta=4997.3,5004.7
XS Rating Curve= 0 ,0
Exp/Cntr=0.3,0.1

Type RM Length L Ch R = 1 ,10441   ,592,592,592
BEGIN DESCRIPTION:
SILVER CREEK 22.0
END DESCRIPTION:
XS GIS Cut Line= 3
      2824747.37     10177869.66      2824513.01     10177479.05
      2823889.39      10177288.5
#Sta/Elev= 30
  4375.8 1340.72  4441.5  1332.9  4505.7 1328.11  4606.7 1314.83  4733.1 1301.75
  4768.3 1294.37  4781.7 1288.33    4826 1274.47  4866.9  1268.1  4872.2 1265.82
  4899.7 1264.22  4937.8 1257.82  4964.5 1249.47  4975.8 1239.56  4992.1  1236.1
  4992.6  1235.6  4999.5  1236.1  5079.5 1248.09  5215.8 1254.13  5257.2 1257.87
  5276.2 1261.59  5281.4 1260.79  5314.2 1269.25    5320  1272.3  5340.9 1276.46
    5347 1279.51  5424.5 1302.12  5450.6 1307.77  5455.9    1312  5483.4 1321.62
#Mann= 3 ,-1 , 0
  4375.8     .12       0  4992.1     .07       0  4999.5     .12       0
Bank Sta=4992.1,4999.5
XS Rating Curve= 0 ,0
Exp/Cntr=0.3,0.1

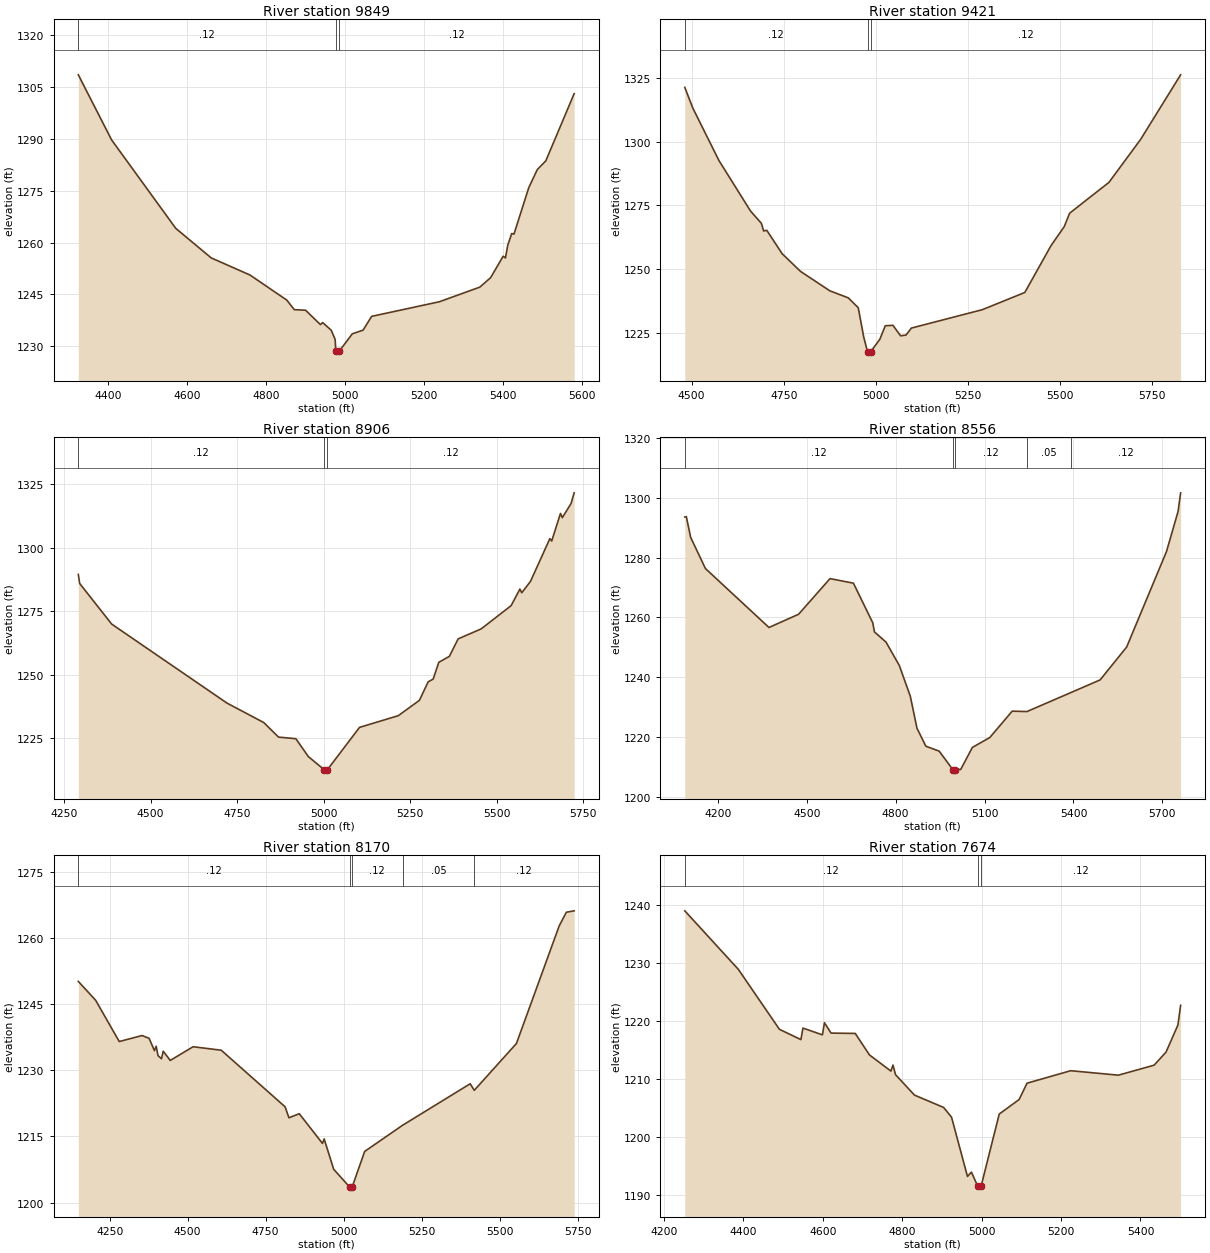
Type RM Length L Ch R = 1 ,9849    ,428,428,428
BEGIN DESCRIPTION:
SILVER CREEK 21.0
END DESCRIPTION:
XS GIS Cut Line= 3
      2825025.12     10176550.25      2824552.08     10176784.61
      2823919.56     10177144.19
#Sta/Elev= 30
  4324.9 1308.49  4409.1 1289.68  4571.6  1264.1  4661.3 1255.56  4759.5 1250.61
  4852.8 1243.35  4871.7 1240.59  4900.4 1240.42  4937.9 1236.27  4943.6 1236.84
  4965.3 1234.64  4975.2 1231.97    4977 1228.52  4977.5 1228.02  4985.2 1228.52
  5018.6  1233.6    5046 1234.67  5067.6 1238.65  5239.2 1242.88  5341.5  1247.1
  5368.9 1249.84  5400.6 1256.04  5406.4 1255.53  5412.3 1259.23  5422.3  1262.6
    5428 1262.43  5465.5 1275.87  5487.1 1281.09  5508.7 1283.63  5580.4 1303.04
#Mann= 3 ,-1 , 0
  4324.9     .12       0    4977     .07       0  4985.2     .12       0
Bank Sta=4977,4985.2
XS Rating Curve= 0 ,0
Exp/Cntr=0.3,0.1

Type RM Length L Ch R = 1 ,9421    ,515,515,515
BEGIN DESCRIPTION:
SILVER CREEK 20.0
END DESCRIPTION:
XS GIS Cut Line= 3
      2824555.69     10176053.11      2824144.09     10176615.34
      2823766.46     10177144.89
#Sta/Elev= 30
  4481.3 1321.27  4503.3 1313.11  4574.3 1292.55    4660  1272.8  4689.4 1267.99
  4695.6 1264.98    4704 1265.27  4745.7  1256.1  4795.9 1249.13  4875.4 1241.54
  4925.6 1238.77  4952.6  1234.9  4967.3 1223.55  4977.8 1217.61  4978.3 1217.11
  4986.1 1217.61  5011.3 1222.56    5026 1227.84  5046.8 1228.01  5067.7  1223.9
  5082.3 1224.19    5097 1226.93  5289.7 1234.14  5405.2 1240.89  5476.5 1259.28
  5512.2 1266.67  5526.9 1271.95  5633.8 1284.05  5719.9  1300.9  5828.5  1326.2
#Mann= 3 ,-1 , 0
  4481.3     .12       0  4977.8     .07       0  4986.1     .12       0
Bank Sta=4977.8,4986.1
XS Rating Curve= 0 ,0
Exp/Cntr=0.3,0.1

Type RM Length L Ch R = 1 ,8906    ,350,350,350
BEGIN DESCRIPTION:
SILVER CREEK 19.0
END DESCRIPTION:
XS GIS Cut Line= 3
      2824131.08     10175842.76      2823818.57     10176220.37
       2823497.4     10177105.77
#Sta/Elev= 30
  4291.4 1289.46  4295.2 1285.93  4387.7 1269.96  4721.1 1238.87    4827 1231.25
  4869.6 1225.53  4919.7  1224.9  4955.6 1217.89    5002 1212.66  5002.5 1212.16
  5010.4 1212.66  5103.6 1229.36  5215.3 1233.94  5276.5 1239.98  5301.8 1247.26
  5316.3 1248.35  5332.4 1254.93    5363 1257.26  5388.3 1264.13  5454.9 1268.07
  5541.4  1277.2  5566.7 1283.72  5572.1 1282.26  5597.4 1286.77  5653.3 1303.55
  5658.6 1302.62  5683.9 1313.45  5689.2 1311.78  5714.5 1317.35  5723.4 1321.54
#Mann= 3 ,-1 , 0
  4291.4     .12       0    5002     .07       0  5010.4     .12       0
Bank Sta=5002,5010.4
XS Rating Curve= 0 ,0
Exp/Cntr=0.3,0.1

Type RM Length L Ch R = 1 ,8556    ,386,386,386
BEGIN DESCRIPTION:
SILVER CREEK 18.0
END DESCRIPTION:
XS GIS Cut Line= 3
      2824065.93     10175625.78      2823562.49      10176007.7
      2823098.77     10176939.47
#Sta/Elev= 30
  4088.8 1293.52    4094 1293.66  4108.6 1286.72  4158.5 1276.32  4372.7 1256.64
  4472.6 1261.05  4578.7 1272.96  4657.7 1271.44    4723 1258.19  4728.6 1255.17
  4767.8 1251.73  4812.5 1243.95  4849.6 1233.68    4872 1223.01  4902.1 1216.99
  4946.9 1215.35  4993.1 1209.17  4993.6 1208.67  5001.5 1209.17  5019.7 1209.24
  5058.9 1216.58  5117.7 1219.88  5193.2 1228.69  5243.3 1228.57  5390.2 1234.86
  5489.9 1239.13  5579.5 1250.12  5713.8 1281.99    5753 1295.42  5761.5 1301.61
#Mann= 5 ,-1 , 0
  4088.8     .12       0  4993.1     .07       0  5001.5     .12       0
  5243.3     .05       0  5390.2     .12       0
Bank Sta=4993.1,5001.5
XS Rating Curve= 0 ,0
Exp/Cntr=0.3,0.1

Type RM Length L Ch R = 1 ,8170    ,496,496,496
BEGIN DESCRIPTION:
SILVER CREEK 17.0
END DESCRIPTION:
XS GIS Cut Line= 3
      2823805.57     10175569.32      2823215.27     10175855.79
      2822820.48     10176701.77
#Sta/Elev= 30
  4149.5 1250.17  4204.9 1245.91  4280.7 1236.53  4353.9 1237.89  4376.5 1237.26
  4393.5 1234.46  4399.1 1235.47    4405 1233.32  4416.1 1232.63  4421.6 1234.34
  4444.2 1232.24  4517.5 1235.35  4607.7 1234.56  4812.3 1221.73  4824.8 1219.23
  4857.9 1220.15  4932.2 1213.42  4937.7 1214.43  4968.2 1207.55  5019.1 1203.54
  5019.6 1203.04  5027.6 1203.54  5067.5 1211.59  5188.9 1217.52  5405.9 1226.95
  5418.9 1225.46  5554.1 1236.08  5691.2 1262.76  5714.1 1265.87  5739.2 1266.19
#Mann= 5 ,-1 , 0
  4149.5     .12       0  5019.1     .07       0  5027.6     .12       0
  5188.9     .05       0  5418.9     .12       0
Bank Sta=5019.1,5027.6
XS Rating Curve= 0 ,0
Exp/Cntr=0.3,0.1

Type RM Length L Ch R = 1 ,7674    ,410,410,410
BEGIN DESCRIPTION:
SILVER CREEK 16.0
END DESCRIPTION:
XS GIS Cut Line= 3
       2823688.4     10175517.24      2823098.08     10175621.41
      2822448.88     10175612.76
#Sta/Elev= 30
  4252.4 1238.94  4387.2 1228.88  4490.7 1218.56  4544.8 1216.79  4549.9 1218.77
    4599 1217.61  4604.1 1219.69  4620.7 1217.91  4681.7 1217.85  4717.5 1214.15
  4771.6 1211.37  4776.7 1212.41  4783.2 1210.75  4830.9 1207.24  4904.2 1205.12
  4924.2 1203.44  4964.3 1193.25  4974.3    1194    4990 1191.57  4990.5 1191.07
  4998.6 1191.57  5044.3 1203.98  5094.3 1206.48  5114.3 1209.29  5224.3 1211.44
  5344.3 1210.67  5434.3 1212.39  5464.3 1214.63  5494.3  1219.3  5501.1 1222.69
#Mann= 3 ,-1 , 0
  4252.4     .12       0    4990     .07       0  4998.6     .12       0
Bank Sta=4990,4998.6
XS Rating Curve= 0 ,0
Exp/Cntr=0.3,0.1

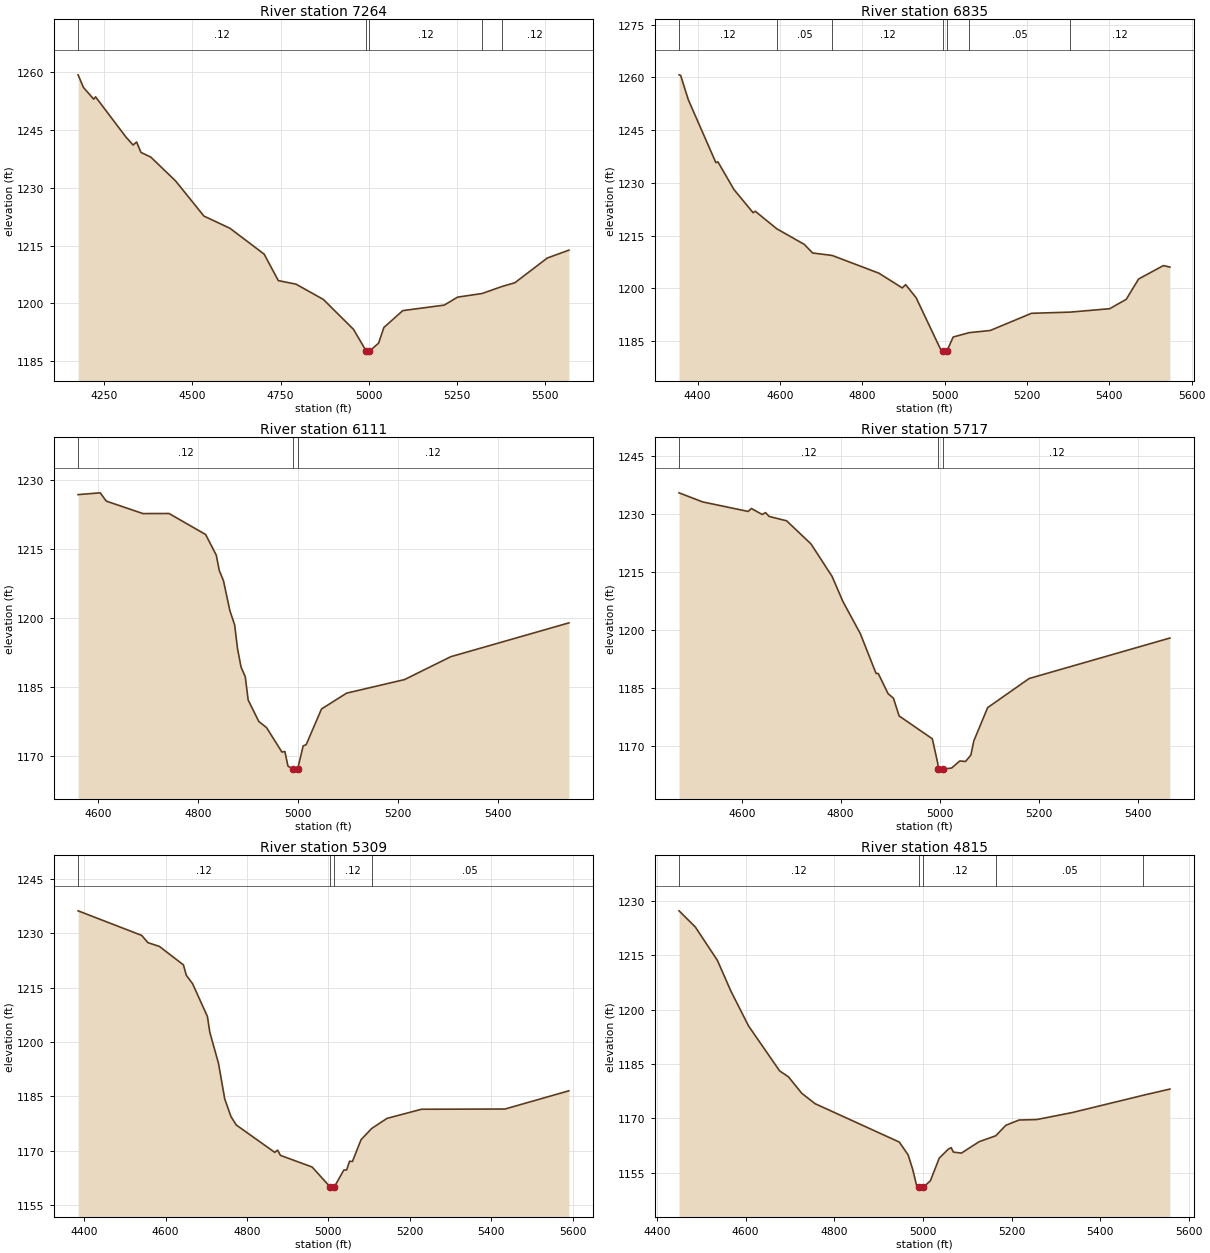
Type RM Length L Ch R = 1 ,7264    ,429,429,429
BEGIN DESCRIPTION:
SILVER CREEK 15.0
END DESCRIPTION:
XS GIS Cut Line= 3
      2823901.01     10175321.93      2823297.74     10175274.19
      2822525.18     10175135.31
#Sta/Elev= 30
  4176.4 1259.33  4191.8 1256.03  4220.8 1253.01  4225.9 1253.62  4312.2 1243.15
  4332.2 1241.11  4342.2 1241.89  4354.4 1239.19  4382.4 1237.97  4452.6 1231.78
  4532.8 1222.66  4606.6 1219.49  4703.4 1212.78  4743.5 1205.91  4793.8 1204.98
  4871.2 1201.01  4956.4 1193.26  4992.7 1187.58  4993.2 1187.08  5001.3 1187.58
  5027.5 1189.66  5042.4 1193.73    5096 1198.12  5213.5 1199.55    5251 1201.61
  5321.1 1202.57    5376 1204.35  5413.6 1205.36    5505 1211.76  5566.5 1213.82
#Mann= 5 ,-1 , 0
  4176.4     .12       0  4992.7     .07       0  5001.3     .12       0
  5321.1     .05       0    5376     .12       0
Bank Sta=4992.7,5001.3
XS Rating Curve= 0 ,0
Exp/Cntr=0.3,0.1

Type RM Length L Ch R = 1 ,6835    ,724,724,724
BEGIN DESCRIPTION:
SILVER CREEK 14.0
END DESCRIPTION:
XS GIS Cut Line= 3
      2823888.06     10174788.08      2823341.14     10174848.84
      2822699.75     10174822.84
#Sta/Elev= 30
  4354.9 1260.74  4358.8 1260.58  4377.4 1253.65  4444.3 1235.77  4449.3 1235.99
  4488.1 1228.13  4534.8 1221.51  4539.9 1221.93  4592.4 1216.93  4659.1  1212.5
  4679.3 1210.06  4727.1 1209.34  4840.2 1204.31  4897.1 1200.11  4905.2 1201.04
  4930.7 1197.34  4990.7 1182.51  4996.3 1182.06  4996.8 1181.56  5005.1 1182.06
  5020.7 1186.14  5059.7 1187.39  5110.8    1188  5210.9 1192.89  5305.3 1193.23
    5401  1194.2  5441.1 1196.87  5471.1 1202.65  5531.2 1206.46  5547.1 1206.04
#Mann= 7 ,-1 , 0
  4354.9     .12       0  4592.4     .05       0  4727.1     .12       0
  4996.3     .07       0  5005.1     .12       0  5059.7     .05       0
  5305.3     .12       0
Bank Sta=4996.3,5005.1
XS Rating Curve= 0 ,0
Exp/Cntr=0.3,0.1

Type RM Length L Ch R = 1 ,6111    ,394,394,394
BEGIN DESCRIPTION:
SILVER CREEK 13.0
END DESCRIPTION:
XS GIS Cut Line= 3
      2823523.44     10173911.34       2822980.9     10174245.55
      2822759.55     10174510.29
#Sta/Elev= 30
  4559.4 1226.83  4603.7 1227.22  4615.9 1225.41  4689.3  1222.7  4741.4 1222.72
  4814.7 1218.14    4836 1213.64  4841.9 1210.34  4850.4 1208.06  4863.2 1201.55
  4872.7 1198.48  4878.6 1193.21  4885.6 1189.25    4894 1187.18  4899.8  1182.1
  4921.1 1177.42  4936.5  1176.1  4967.3 1170.77  4973.2 1170.89  4979.6 1167.67
    4990 1167.11  4990.5 1166.61  4998.9 1167.11  5009.9 1172.12  5015.8 1172.35
  5046.6 1180.15    5097  1183.6  5212.8 1186.55  5305.2 1191.53  5541.7  1198.9
#Mann= 3 ,-1 , 0
  4559.4     .12       0    4990     .07       0  4998.9     .12       0
Bank Sta=4990,4998.9
XS Rating Curve= 0 ,0
Exp/Cntr=0.3,0.1

Type RM Length L Ch R = 1 ,5717    ,408,408,408
BEGIN DESCRIPTION:
SILVER CREEK 12.0
END DESCRIPTION:
XS GIS Cut Line= 3
      2823163.22     10173533.71      2822898.43     10173833.22
      2822633.67     10174362.74
#Sta/Elev= 30
  4473.4 1235.55  4520.9  1233.2  4612.9 1230.73  4619.6 1231.48  4641.4 1229.94
  4648.1 1230.42  4655.6 1229.42  4690.7  1228.3  4740.1 1222.29  4782.7 1213.86
  4804.5 1207.37  4839.6 1199.07  4871.5 1188.71  4875.9 1188.71  4895.8 1183.47
  4906.6  1182.3  4918.1  1177.7  4985.2 1171.77    4996 1165.52  4997.5 1163.89
    4998 1163.39  5006.5 1163.89  5024.3 1164.21  5040.8 1166.03  5052.3 1165.89
  5063.1 1167.57    5069 1171.23    5097 1179.86  5180.9 1187.41  5465.2  1197.9
#Mann= 3 ,-1 , 0
  4473.4     .12       0  4997.5     .07       0  5006.5     .12       0
Bank Sta=4997.5,5006.5
XS Rating Curve= 0 ,0
Exp/Cntr=0.3,0.1

Type RM Length L Ch R = 1 ,5309    ,494,494,494
BEGIN DESCRIPTION:
SILVER CREEK 11.0
END DESCRIPTION:
XS GIS Cut Line= 3
      2822985.25     10173416.54      2822584.89     10173666.52
       2822065.1     10174184.78
#Sta/Elev= 30
    4385 1236.23  4541.3 1229.44  4556.7 1227.43  4584.9 1226.39  4643.8  1221.3
    4651 1218.42  4666.4 1216.09  4702.8 1207.03  4708.8 1202.62    4730  1194.1
  4745.4 1184.23  4760.7 1179.38  4773.5 1177.08  4868.2  1169.5  4875.2 1170.11
  4882.3 1168.66  4960.1 1165.45  5005.1 1159.84  5005.6 1159.34  5014.1 1159.84
  5037.9 1164.61  5044.9 1164.64    5052 1167.05  5059.1 1166.97  5080.3 1173.01
  5106.2 1176.08  5143.9 1178.88  5228.8 1181.41  5433.9 1181.47    5591 1186.51
#Mann= 4 ,-1 , 0
    4385     .12       0  5005.1     .07       0  5014.1     .12       0
  5106.2     .05       0
Bank Sta=5005.1,5014.1
XS Rating Curve= 0 ,0
Exp/Cntr=0.3,0.1

Type RM Length L Ch R = 1 ,4815    ,358,358,358
BEGIN DESCRIPTION:
SILVER CREEK 10.0
END DESCRIPTION:
XS GIS Cut Line= 3
      2822872.37     10173364.47       2822322.5       10173359.
      2821765.65     10173351.45
#Sta/Elev= 30
  4450.1 1227.27  4486.8 1222.81  4536.8 1213.55  4566.8 1205.17  4606.8 1195.51
  4676.8 1183.12  4696.8 1181.46  4726.8 1176.93  4756.8 1174.06  4946.8 1163.46
  4966.8 1159.89  4976.8    1156  4986.8 1150.99  4991.4 1150.98  4991.9 1150.48
  5000.4 1150.98  5016.8 1152.77  5036.8 1159.03  5056.8 1161.46  5063.7 1161.93
  5068.7  1160.7  5086.8 1160.42  5126.8 1163.57  5164.3  1165.2  5186.8 1168.08
  5216.8 1169.55  5256.8 1169.68  5336.8 1171.61  5496.9 1176.38  5556.9 1178.09
#Mann= 5 ,-1 , 0
  4450.1     .12       0  4991.4     .07       0  5000.4     .12       0
  5164.3     .05       0  5496.9     .12       0
Bank Sta=4991.4,5000.4
XS Rating Curve= 0 ,0
Exp/Cntr=0.3,0.1

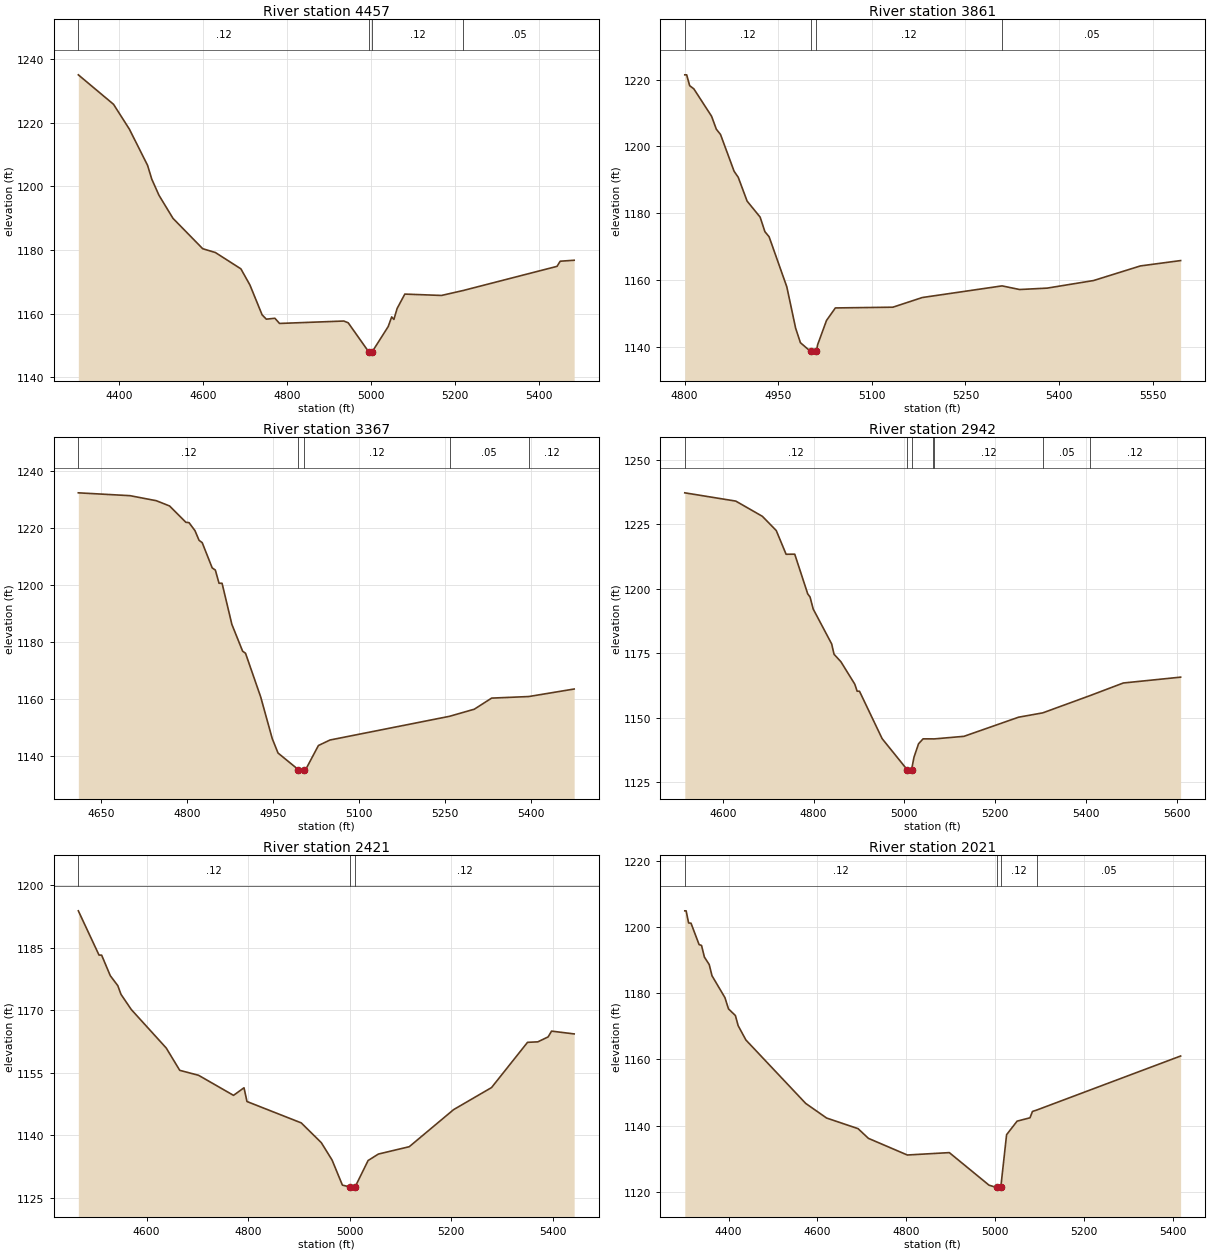
Type RM Length L Ch R = 1 ,4457    ,596,596,596
BEGIN DESCRIPTION:
SILVER CREEK 9.0
END DESCRIPTION:
XS GIS Cut Line= 3
      2823028.66     10173125.76      2822455.72     10173043.29
      2821887.18     10172847.99
#Sta/Elev= 30
  4303.8 1235.11  4387.6 1225.83  4425.3 1218.01  4468.5 1206.65  4478.6 1202.28
  4495.8 1197.19  4529.1 1189.94  4599.8 1180.39  4630.1 1179.18  4690.7 1174.05
  4712.2 1168.97  4741.2 1159.57  4751.3 1158.22  4771.6  1158.5  4782.7 1156.87
  4935.6 1157.63  4946.1 1157.07  4994.4 1148.03  4994.9 1147.53  5003.5 1148.03
  5041.3  1155.9  5049.5 1158.93  5054.8 1158.13  5062.4 1161.56  5080.8 1166.11
  5168.2 1165.68  5220.4 1167.26  5443.1 1174.84  5450.5 1176.45  5483.8 1176.76
#Mann= 4 ,-1 , 0
  4303.8     .12       0  4994.4     .07       0  5003.5     .12       0
  5220.4     .05       0
Bank Sta=4994.4,5003.5
XS Rating Curve= 0 ,0
Exp/Cntr=0.3,0.1

Type RM Length L Ch R = 1 ,3861    ,494,494,494
BEGIN DESCRIPTION:
SILVER CREEK 8.0
END DESCRIPTION:
XS GIS Cut Line= 3
      2822985.25     10172904.41      2822698.54     10172652.26
      2822339.57     10172449.26
#Sta/Elev= 30
  4800.4 1221.48  4803.4 1221.48  4808.2 1218.23  4814.9 1217.27  4843.3 1209.06
  4850.9 1205.18  4857.6  1203.6  4879.4 1192.56    4886 1190.76  4900.2 1183.62
  4921.1 1178.81  4928.7 1174.46  4935.4 1172.95  4963.8 1157.92    4978 1145.48
  4985.6 1141.17  5001.9 1138.54  5002.4 1138.04  5011.1 1138.54  5013.2 1140.57
  5027.4 1147.84  5041.6 1151.59  5133.7 1151.81  5180.8 1154.71  5308.6  1158.2
  5336.7 1157.11  5380.8 1157.53  5455.1  1159.8  5530.1 1164.18  5594.6 1165.79
#Mann= 4 ,-1 , 0
  4800.4     .12       0  5001.9     .07       0  5011.1     .12       0
  5308.6     .05       0
Bank Sta=5001.9,5011.1
XS Rating Curve= 0 ,0
Exp/Cntr=0.3,0.1

Type RM Length L Ch R = 1 ,3367    ,425,425,425
BEGIN DESCRIPTION:
SILVER CREEK 7.0
END DESCRIPTION:
XS GIS Cut Line= 3
      2823280.36     10172426.96      2823054.68      10172322.8
      2822442.67     10172253.35
#Sta/Elev= 30
  4610.3 1232.39  4700.5 1231.39  4746.4 1229.62  4769.4 1227.78  4797.8 1222.06
  4803.3 1221.94  4813.7 1219.12  4820.8 1215.74  4826.3 1214.92  4843.7 1206.07
  4849.2 1205.31  4855.6 1200.69  4860.9 1200.69    4878 1186.27  4896.8 1176.85
  4901.8 1176.15  4928.3  1160.8  4948.4 1146.22  4958.5 1141.16  4994.1 1135.32
  4994.6 1134.82  5003.3 1135.32  5008.8 1136.17  5028.9  1143.8  5049.1 1145.73
  5257.5 1154.04  5300.7 1156.53  5330.9 1160.42  5395.7 1160.97  5474.8 1163.61
#Mann= 5 ,-1 , 0
  4610.3     .12       0  4994.1     .07       0  5003.3     .12       0
  5257.5     .05       0  5395.7     .12       0
Bank Sta=4994.1,5003.3
XS Rating Curve= 0 ,0
Exp/Cntr=0.3,0.1

Type RM Length L Ch R = 1 ,2942    ,521,521,521
BEGIN DESCRIPTION:
SILVER CREEK 6.0
END DESCRIPTION:
XS GIS Cut Line= 3
      2823423.55     10171958.21      2823050.34     10171888.78
      2822339.63     10171849.77
#Sta/Elev= 30
  4516.6 1237.26  4628.9 1234.05  4687.4 1228.14  4717.9 1222.64  4739.6 1213.43
  4758.6 1213.47  4787.2 1198.07  4792.3 1196.86  4799.2 1192.21  4839.9 1178.65
  4845.1 1174.66  4860.3 1171.73  4890.8 1163.04    4896 1160.31  4901.1 1160.31
    4951 1141.91  5006.4 1129.82  5006.9 1129.32  5015.7 1129.82  5021.1 1134.72
  5031.1 1139.92  5041.1 1141.84  5061.9 1141.83  5065.2 1141.81  5131.2 1142.82
  5251.4 1150.24  5304.6 1151.92  5408.7 1158.62  5481.8  1163.5    5608 1165.77
#Mann= 7 ,-1 , 0
  4516.6     .12       0  5006.4     .07       0  5015.7     .12       0
  5061.9     .05       0  5065.2     .12       0  5304.6     .05       0
  5408.7     .12       0
Bank Sta=5006.4,5015.7
XS Rating Curve= 0 ,0
Exp/Cntr=0.3,0.1

Type RM Length L Ch R = 1 ,2421    ,400,400,400
BEGIN DESCRIPTION:
SILVER CREEK 5.0
END DESCRIPTION:
XS GIS Cut Line= 3
      2823345.46      10171472.1       2823002.6     10171359.26
      2822395.01     10171454.74
#Sta/Elev= 30
  4465.8 1193.84  4506.5 1183.24  4511.7 1183.21  4528.7 1178.29  4543.5  1175.9
  4549.8 1173.81  4570.1 1170.17  4638.9 1160.94  4665.4  1155.6  4702.5 1154.41
  4771.3  1149.6  4791.9 1151.42  4797.8 1148.12  4904.6    1143  4944.1 1138.26
  4965.3 1134.09  4985.6 1128.08  5001.2 1127.62  5001.7 1127.12  5010.5 1127.62
  5036.2 1133.98  5056.5 1135.53  5117.2 1137.29  5204.5 1146.18  5279.2 1151.47
    5350 1162.31  5370.3 1162.43  5390.5 1163.61  5397.3    1165  5441.8 1164.33
#Mann= 3 ,-1 , 0
  4465.8     .12       0  5001.2     .07       0  5010.5     .12       0
Bank Sta=5001.2,5010.5
XS Rating Curve= 0 ,0
Exp/Cntr=0.3,0.1

Type RM Length L Ch R = 1 ,2021    ,568,568,568
BEGIN DESCRIPTION:
SILVER CREEK 4.0
END DESCRIPTION:
XS GIS Cut Line= 3
      2823406.27     10171272.47      2822655.68     10170953.11
      2822355.88     10170925.23
#Sta/Elev= 30
  4301.3  1204.9  4304.3  1204.9  4309.9 1201.24  4315.3 1201.16  4333.5  1194.7
    4339 1194.45  4345.4 1190.95  4356.3 1188.67  4362.6 1185.28  4391.7 1178.68
  4399.7 1175.28  4415.3 1173.26  4421.5  1170.2    4439 1165.87  4573.6 1146.72
  4620.7  1142.3  4691.6 1139.09  4714.9 1136.16  4802.5 1131.13  4897.1 1131.85
  4986.6 1122.01  5003.6 1121.32  5004.1 1120.82    5013 1121.32  5026.1 1137.27
  5049.8 1141.36  5078.8 1142.37  5084.4 1144.29  5094.8 1144.75  5418.1 1161.04
#Mann= 4 ,-1 , 0
  4301.3     .12       0  5003.6     .07       0    5013     .12       0
  5094.8     .05       0
Bank Sta=5003.6,5013
XS Rating Curve= 0 ,0
Exp/Cntr=0.3,0.1