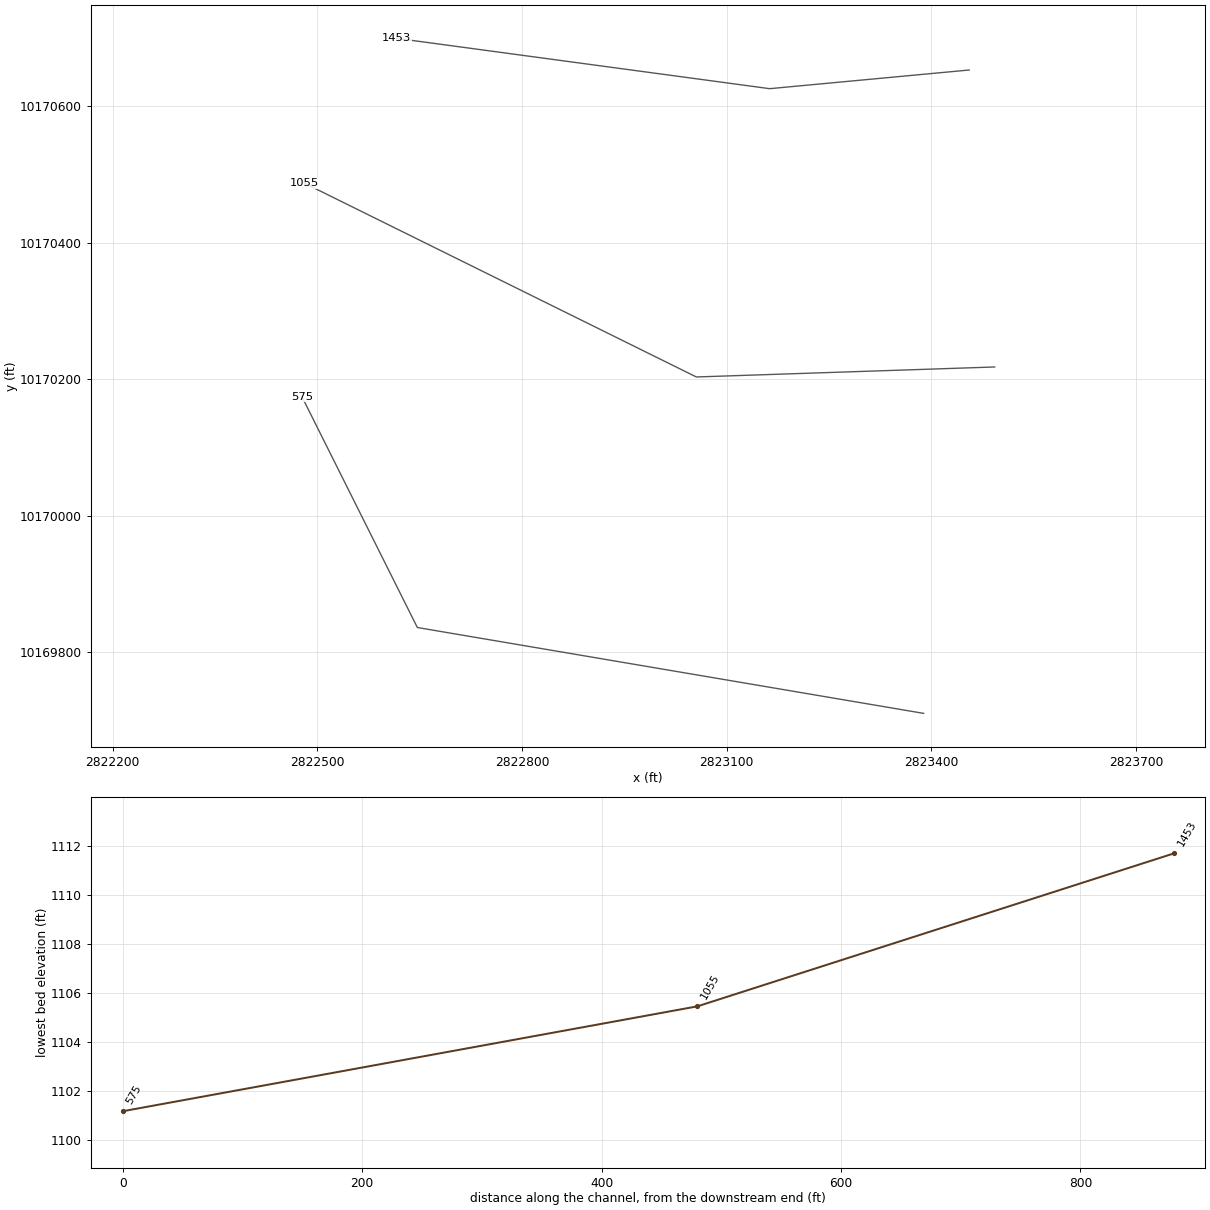
HEC-RAS study SILVER CREEK.prj: SILVER CREEK Base Level Engineering

--- SILVER CREEK.g01 (geometry) --- (continued)

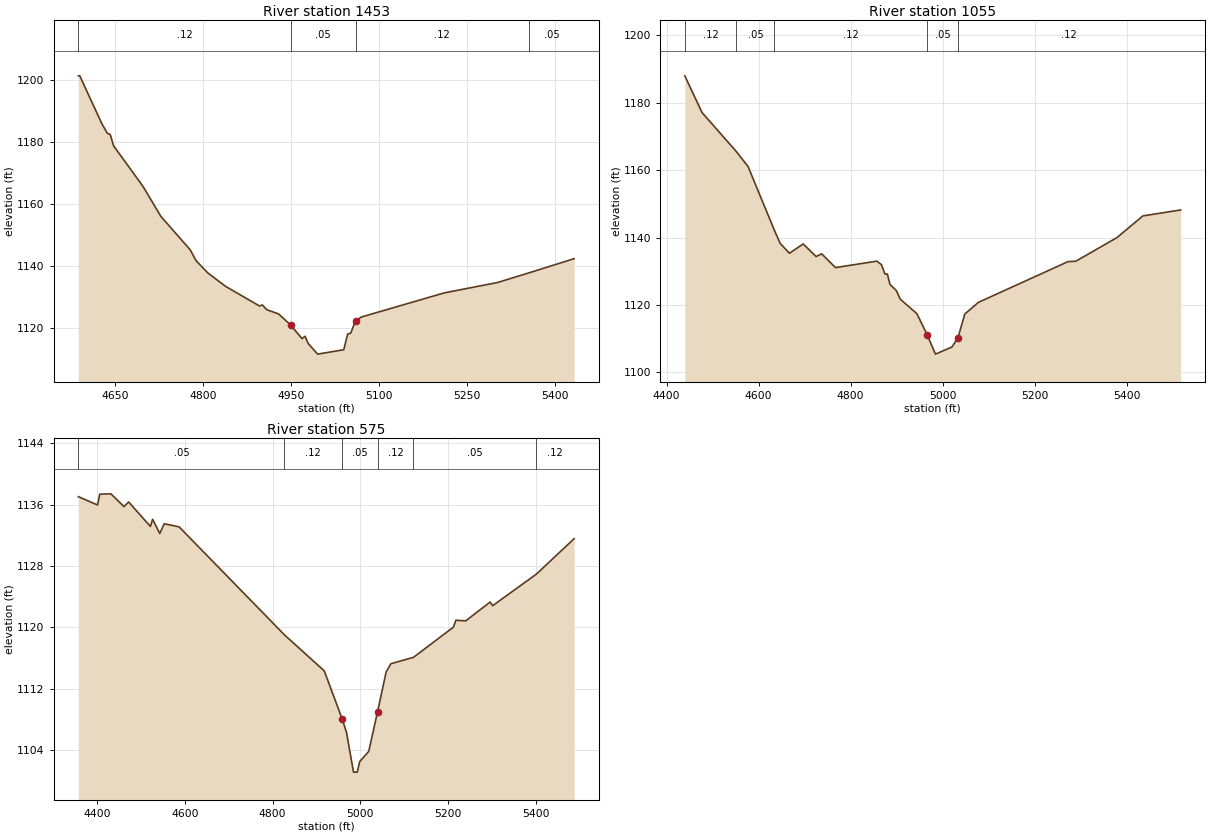
Type RM Length L Ch R = 1 ,1453    ,398,398,398
BEGIN DESCRIPTION:
SILVER CREEK 3.0
END DESCRIPTION:
XS GIS Cut Line= 3
      2823455.66     10170653.11      2823163.19     10170625.75
      2822616.29     10170699.54
#Sta/Elev= 30
  4587.7  1201.4  4590.2  1201.4  4627.9 1185.93  4637.1 1182.88  4642.1 1182.49
  4647.9 1178.82  4698.2  1165.7  4728.3 1156.13  4778.5 1145.31  4788.6 1141.78
  4808.6 1137.85  4838.8 1133.53  4896.6 1127.21  4901.6 1127.53  4909.2 1125.99
  4929.4 1124.63  4949.6 1121.09  4969.3 1116.67  4974.3 1117.45  4979.8 1115.08
  4995.8 1111.68  5040.4  1113.1    5047 1118.17  5052.1 1118.41  5060.6 1122.44
  5070.7 1123.66  5211.9 1131.43  5302.7 1134.77  5356.5  1137.9  5433.3 1142.46
#Mann= 4 ,-1 , 0
  4587.7     .12       0  4949.6     .05       0  5060.6     .12       0
  5356.5     .05       0
Bank Sta=4949.6,5060.6
XS Rating Curve= 0 ,0
Exp/Cntr=0.3,0.1

Type RM Length L Ch R = 1 ,1055    ,480,480,480
BEGIN DESCRIPTION:
SILVER CREEK 2.0
END DESCRIPTION:
XS GIS Cut Line= 3
      2823493.06     10170217.77      2823055.68     10170203.11
      2822481.72     10170486.88
#Sta/Elev= 30
  4439.7 1187.96  4477.1 1177.09  4551.9 1165.48  4577.2 1161.08  4634.7 1142.08
  4647.2 1138.25  4667.2 1135.35  4697.2 1138.11  4725.1 1134.37  4737.2 1135.19
  4767.3  1131.1  4857.3 1133.01  4867.3 1131.95  4874.8 1129.19  4880.1 1129.19
  4885.7 1126.13  4899.6 1124.27  4908.2 1121.73  4944.3 1117.44  4966.6 1111.16
  4984.6 1105.44  5020.4 1107.55  5033.5 1110.26  5048.4 1117.33  5078.1  1120.8
  5272.8 1132.87  5289.6 1132.98  5379.3    1140  5435.4 1146.42  5517.6 1148.19
#Mann= 5 ,-1 , 0
  4439.7     .12       0  4551.9     .05       0  4634.7     .12       0
  4966.6     .05       0  5033.5     .12       0
Bank Sta=4966.6,5033.5
XS Rating Curve= 0 ,0
Exp/Cntr=0.3,0.1

Type RM Length L Ch R = 1 ,575     ,0,0,0
BEGIN DESCRIPTION:
SILVER CREEK 1.0
END DESCRIPTION:
XS GIS Cut Line= 3
      2823388.91     10169709.95      2822646.69     10169835.82
      2822477.43     10170174.35
#Sta/Elev= 30
  4356.7 1137.03  4400.5 1135.95  4405.6 1137.35    4431  1137.4  4460.8 1135.74
  4471.5 1136.34  4521.2 1133.15  4526.2 1134.08  4542.5 1132.24  4552.7  1133.5
  4586.6  1133.1  4826.9 1119.04  4917.8 1114.35  4958.4 1108.13  4968.5 1106.36
  4984.6 1101.16  4993.1 1101.16  4998.7 1102.53  5019.3 1103.86  5039.5 1109.04
  5059.1 1114.22    5070 1115.28  5121.4 1116.11  5212.5 1120.04  5218.3 1120.94
  5240.6 1120.86  5296.4 1123.31    5302 1122.83  5401.7 1126.94    5488 1131.56
#Mann= 6 ,-1 , 0
  4356.7     .05       0  4826.9     .12       0  4958.4     .05       0
  5039.5     .12       0  5121.4     .05       0  5401.7     .12       0
Bank Sta=4958.4,5039.5
XS Rating Curve= 0 ,0
Exp/Cntr=0.3,0.1

Chan Stop Cuts=-1
Use User Specified Reach Order=0
Composite Channel Slope=5