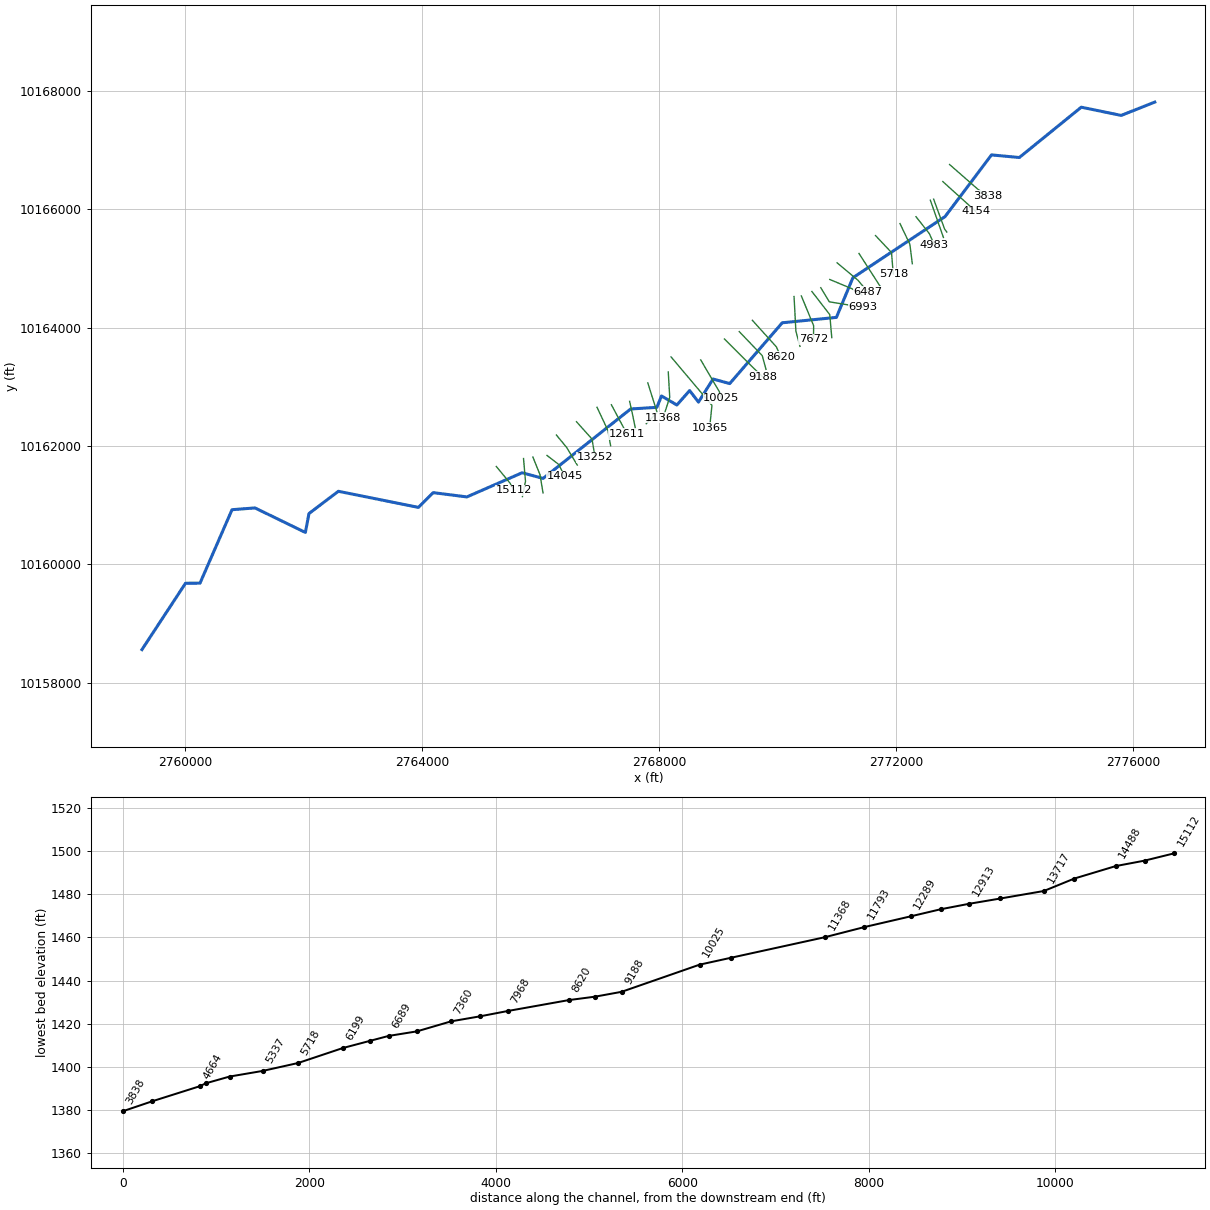
--- SOUTH HELMS CREEK.prj (project) ---

Proj Title=SOUTH HELMS CREEK Base Level Engineering
Current Plan=p01
Default Exp/Contr=0.3,0.1
English Units
Geom File=g01
Flow File=f01
Plan File=p01
Y Axis Title=Elevation
X Axis Title(PF)=Main Channel Distance
X Axis Title(XS)=Station
BEGIN DESCRIPTION:
SOUTH HELMS CREEK
END DESCRIPTION:
DSS Export Rating Curves= 0
DSS Export Rating Curve Sorted= 0
DSS Export Volume Flow Curves= 0
DXF OffsetX= 0
DXF OffsetY= 0
DXF ScaleX= 1
DXF ScaleY= 10

--- SOUTH HELMS CREEK.p01 (plan) ---

Plan Title=Multiple Run
Short Identifier=Multiple
Geom File=g01
Flow File=f01
Subcritical Flow
K Sum by GR= 0
Std Step Tol= 0.01
Critical Tol= 0.01
Num of Std Step Trials= 20
Max Error Tol= 0.3
Flow Tol Ratio= 0.001
Split Flow NTrial= 30
Split Flow Tol= 0.02
Split Flow Ratio= 0.02
Log Output Level= 0
Friction Slope Method= 1
Unsteady Friction Slope Method= 2
Unsteady Bridges Friction Slope Method= 1
Parabolic Critical Depth
Global Vel Dist=  1 , 1 , 1
Global Log Level= 0
CheckData=True
Encroach Param= -1, 0, 0, 0
BEGIN DESCRIPTION:
Multiple Run
END DESCRIPTION:

--- SOUTH HELMS CREEK.f01 (steady flow) ---

Flow Title=Multiple
Program Version=4.10
Number of Profiles= 7
Profile Names=10-year,25-year,50-year,1pct_min,100-year,1pct_plu,500-year
River Rch & RM=SOUTH HELMS CREE,Reach-1         ,15112
     662    1105    2017    1493    2835    5383    4062
River Rch & RM=SOUTH HELMS CREE,Reach-1         ,10365
     980    1693    2943    2025    4184    8643    5995
Boundary for River Rch & Prof#=SOUTH HELMS CREE,Reach-1         , 1
Up Type= 0
Dn Type= 3
Dn Slope=0.01074
Boundary for River Rch & Prof#=SOUTH HELMS CREE,Reach-1         , 2
Up Type= 0
Dn Type= 3
Dn Slope=0.01074
Boundary for River Rch & Prof#=SOUTH HELMS CREE,Reach-1         , 3
Up Type= 0
Dn Type= 3
Dn Slope=0.01074
Boundary for River Rch & Prof#=SOUTH HELMS CREE,Reach-1         , 4
Up Type= 0
Dn Type= 3
Dn Slope=0.01074
Boundary for River Rch & Prof#=SOUTH HELMS CREE,Reach-1         , 5
Up Type= 0
Dn Type= 3
Dn Slope=0.01074
Boundary for River Rch & Prof#=SOUTH HELMS CREE,Reach-1         , 6
Up Type= 0
Dn Type= 3
Dn Slope=0.01074
Boundary for River Rch & Prof#=SOUTH HELMS CREE,Reach-1         , 7
Up Type= 0
Dn Type= 3
Dn Slope=0.01074
DSS Import GetInterval= 0
DSS Import GetPeak= 0
DSS Import FillOption= 0

--- SOUTH HELMS CREEK.g01 (geometry) ---

Geom Title=Existing Conditions
Program Version=4.10

River Reach=SOUTH HELMS CREE,Reach-1
Reach XY= 30
        2759275.       10158560.      2760010.75       10159681.
        2760255.       10159682.       2760795.5       10160923.
      2761182.75       10160953.       2762033.5       10160539.
      2762094.25       10160858.        2762590.       10161234.
        2763942.       10160962.       2764190.5       10161211.
      2764759.25       10161139.      2765692.25       10161547.
        2766046.       10161451.      2767522.75       10162624.
       2767966.5       10162652.      2768043.75       10162844.
      2768302.75       10162691.      2768518.75       10162935.
        2768668.       10162740.       2768913.5       10163130.
       2769195.5       10163053.        2770082.       10164080.
        2770996.       10164171.       2771273.5       10164840.
        2772830.       10165874.       2773613.5       10166915.
      2774083.25       10166871.      2775128.75       10167721.
       2775802.5       10167582.        2776369.       10167807.

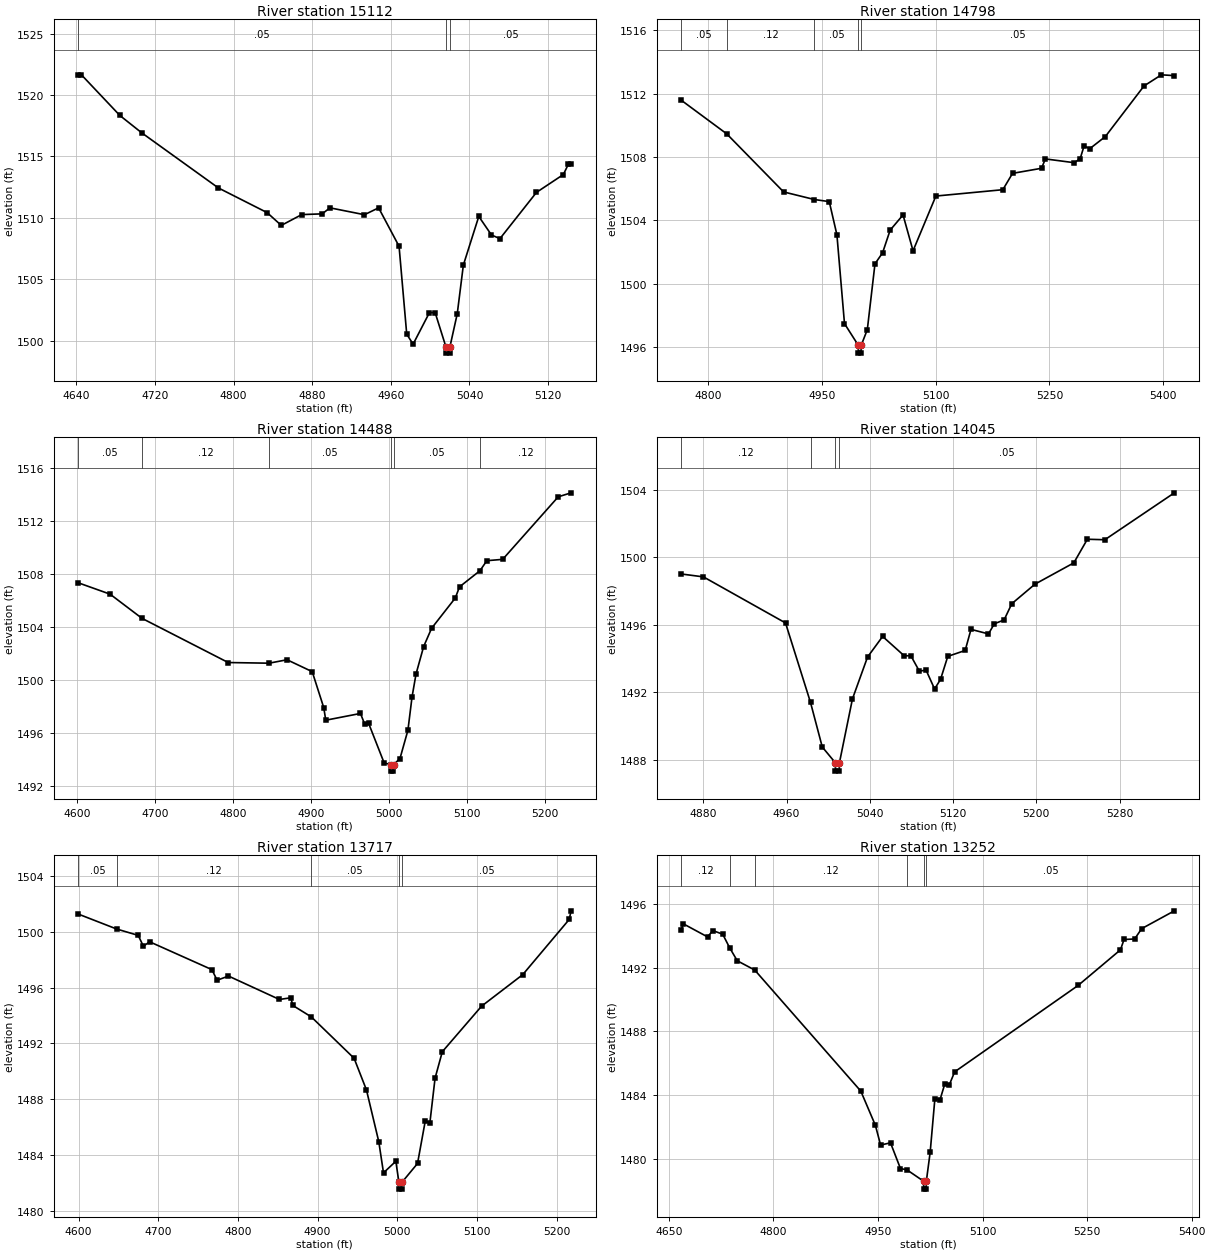
Type RM Length L Ch R = 1 ,15112   ,314,314,314
BEGIN DESCRIPTION:
SOUTH HELMS CREEK 31.0
END DESCRIPTION:
XS GIS Cut Line= 3
      2765255.66     10161653.14       2765483.5       10161377.
      2765555.69      10161253.1
#Sta/Elev= 30
    4642 1521.65  4645.3 1521.65  4684.4 1518.34  4706.6 1516.93  4784.6 1512.44
  4834.2 1510.43  4848.6 1509.39  4869.4 1510.27  4890.2 1510.33  4898.1 1510.82
  4933.2 1510.26  4947.6 1510.82  4968.4 1507.69  4976.2 1500.53  4982.7 1499.72
  4999.3 1502.29  5005.1 1502.29  5016.1 1499.49  5016.3 1498.99  5019.8 1498.99
  5020.1 1499.49  5027.6  1502.2  5033.8 1506.16  5049.5 1510.12  5062.4 1508.61
    5071 1508.31  5108.2 1512.08  5135.5 1513.53  5140.5 1514.35  5143.4 1514.35
#Mann= 3 ,-1 , 0
    4642     .05       0  5016.1     .05       0  5020.1     .05       0
Bank Sta=5016.1,5020.1
XS Rating Curve= 0 ,0
Exp/Cntr=0.3,0.1

Type RM Length L Ch R = 1 ,14798   ,310,310,310
BEGIN DESCRIPTION:
SOUTH HELMS CREEK 30.0
END DESCRIPTION:
XS GIS Cut Line= 3
       2765715.1     10161787.31      2765748.65     10161403.07
      2765696.81      10161143.9
#Sta/Elev= 30
  4764.8 1511.57  4824.5 1509.46  4899.5  1505.8  4940.2 1505.32  4959.7 1505.19
  4969.8  1503.1  4979.8  1497.5  4997.9 1496.14  4998.1 1495.64  5001.6 1495.64
  5001.9 1496.14  5009.9 1497.12    5020 1501.27    5030 1501.96    5040 1503.39
    5057 1504.35  5070.2 1502.09  5100.3 1505.54  5188.6 1505.94  5201.4 1506.97
  5239.6 1507.29  5244.7 1507.88    5283 1507.64  5290.6  1507.9  5295.7 1508.69
  5303.4 1508.53  5323.8 1509.29  5374.8 1512.48  5397.7 1513.18  5414.8 1513.13
#Mann= 5 ,-1 , 0
  4764.8     .05       0  4824.5     .12       0  4940.2     .05       0
  4997.9     .05       0  5001.9     .05       0
Bank Sta=4997.9,5001.9
XS Rating Curve= 0 ,0
Exp/Cntr=0.3,0.1

Type RM Length L Ch R = 1 ,14488   ,443,443,443
BEGIN DESCRIPTION:
SOUTH HELMS CREEK 29.0
END DESCRIPTION:
XS GIS Cut Line= 3
      2765873.68     10161811.74      2765992.62     10161515.91
      2766044.18     10161206.52
#Sta/Elev= 30
  4601.5 1507.35  4642.4 1506.49  4683.4 1504.66    4794 1501.32  4846.4 1501.27
  4869.5 1501.53  4901.8 1500.63  4916.6 1497.91  4919.2 1496.96  4963.7 1497.47
  4969.1 1496.67  4974.2 1496.72  4994.1 1493.73  5002.3 1493.61  5002.5 1493.11
    5006 1493.11  5006.3 1493.61  5014.4 1494.06  5024.6  1496.2  5029.9 1498.72
    5035 1500.45  5044.8 1502.53    5055 1503.91  5085.4  1506.2  5090.8 1507.04
    5117 1508.26  5125.9 1509.02  5146.2 1509.12  5217.5 1513.85    5234 1514.15
#Mann= 6 ,-1 , 0
  4601.5     .05       0  4683.4     .12       0  4846.4     .05       0
  5002.3     .05       0  5006.3     .05       0    5117     .12       0
Bank Sta=5002.3,5006.3
XS Rating Curve= 0 ,0
Exp/Cntr=0.3,0.1

Type RM Length L Ch R = 1 ,14045   ,328,328,328
BEGIN DESCRIPTION:
SOUTH HELMS CREEK 28.0
END DESCRIPTION:
XS GIS Cut Line= 3
      2766111.57     10161839.15      2766309.78     10161686.69
      2766409.75     10161486.75
#Sta/Elev= 30
    4859 1499.02  4880.1 1498.85    4959 1496.12    4983 1491.41  4994.3 1488.77
  5006.8 1487.84    5007 1487.34  5010.5 1487.34  5010.8 1487.84  5023.3 1491.62
  5037.8  1494.1  5052.3 1495.32  5073.1 1494.17  5079.4 1494.18  5087.6 1493.26
    5094 1493.33  5102.2 1492.21  5107.9 1492.77  5114.9 1494.14  5131.6 1494.49
  5137.2 1495.74    5154 1495.47  5159.6 1496.07    5169  1496.3  5176.4 1497.26
  5198.7 1498.42    5236 1499.68    5249 1501.08  5265.8 1501.05  5332.6 1503.83
#Mann= 4 ,-1 , 0
    4859     .12       0    4983     .05       0  5006.8     .03       0
  5010.8     .05       0
Bank Sta=5006.8,5010.8
XS Rating Curve= 0 ,0
Exp/Cntr=0.3,0.1

Type RM Length L Ch R = 1 ,13717   ,465,465,465
BEGIN DESCRIPTION:
Mapping XS 82919e88
END DESCRIPTION:
XS GIS Cut Line= 3
      2766270.53     10162183.49      2766443.19     10161974.25
      2766622.47      10161676.9
#Sta/Elev= 30
  4599.6 1501.29  4648.1 1500.21  4674.9 1499.76  4681.4 1498.98  4689.2  1499.3
  4767.4  1497.3  4773.9 1496.54  4788.2 1496.84  4852.1 1495.16  4866.4 1495.28
  4868.9 1494.73  4892.1 1493.91  4945.8 1490.94  4961.3 1488.67  4976.8 1484.95
  4982.7 1482.72  4998.2 1483.55    5002 1482.05  5002.3 1481.55  5005.8 1481.55
    5006 1482.05  5025.4 1483.39  5035.1 1486.44  5040.9 1486.31  5047.4 1489.51
  5056.5 1491.41  5105.8 1494.68  5157.4 1496.94  5215.7  1500.9  5218.1 1501.52
#Mann= 5 ,-1 , 0
  4599.6     .05       0  4648.1     .12       0  4892.1     .05       0
    5002     .03       0    5006     .05       0
Bank Sta=5002,5006
XS Rating Curve= 0 ,0
Exp/Cntr=0.3,0.1

Type RM Length L Ch R = 1 ,13252   ,339,339,339
BEGIN DESCRIPTION:
SOUTH HELMS CREEK 27.0
END DESCRIPTION:
XS GIS Cut Line= 3
      2766608.66     10162409.42      2766870.91     10162116.68
      2766922.54     10161806.88
#Sta/Elev= 30
  4668.1 1494.39  4670.5 1494.76  4705.6 1493.93  4713.1 1494.33  4727.3  1494.1
  4737.2 1493.25  4748.2 1492.43  4773.2 1491.85  4925.4 1484.24  4946.3 1482.09
  4953.8 1480.85    4968 1480.99  4982.3 1479.37  4991.3  1479.3  5015.4 1478.58
  5015.6 1478.08  5019.1 1478.08  5019.4 1478.58  5024.9  1480.4  5031.6 1483.74
  5039.1 1483.71  5045.8 1484.68  5052.5 1484.65    5060 1485.45  5237.1 1490.88
  5297.9 1493.12    5303 1493.77  5318.2  1493.8  5328.3 1494.45  5375.2 1495.57
#Mann= 6 ,-1 , 0
  4668.1     .12       0  4737.2     .05       0  4773.2     .12       0
  4991.3     .05       0  5015.4     .03       0  5019.4     .05       0
Bank Sta=5015.4,5019.4
XS Rating Curve= 0 ,0
Exp/Cntr=0.3,0.1

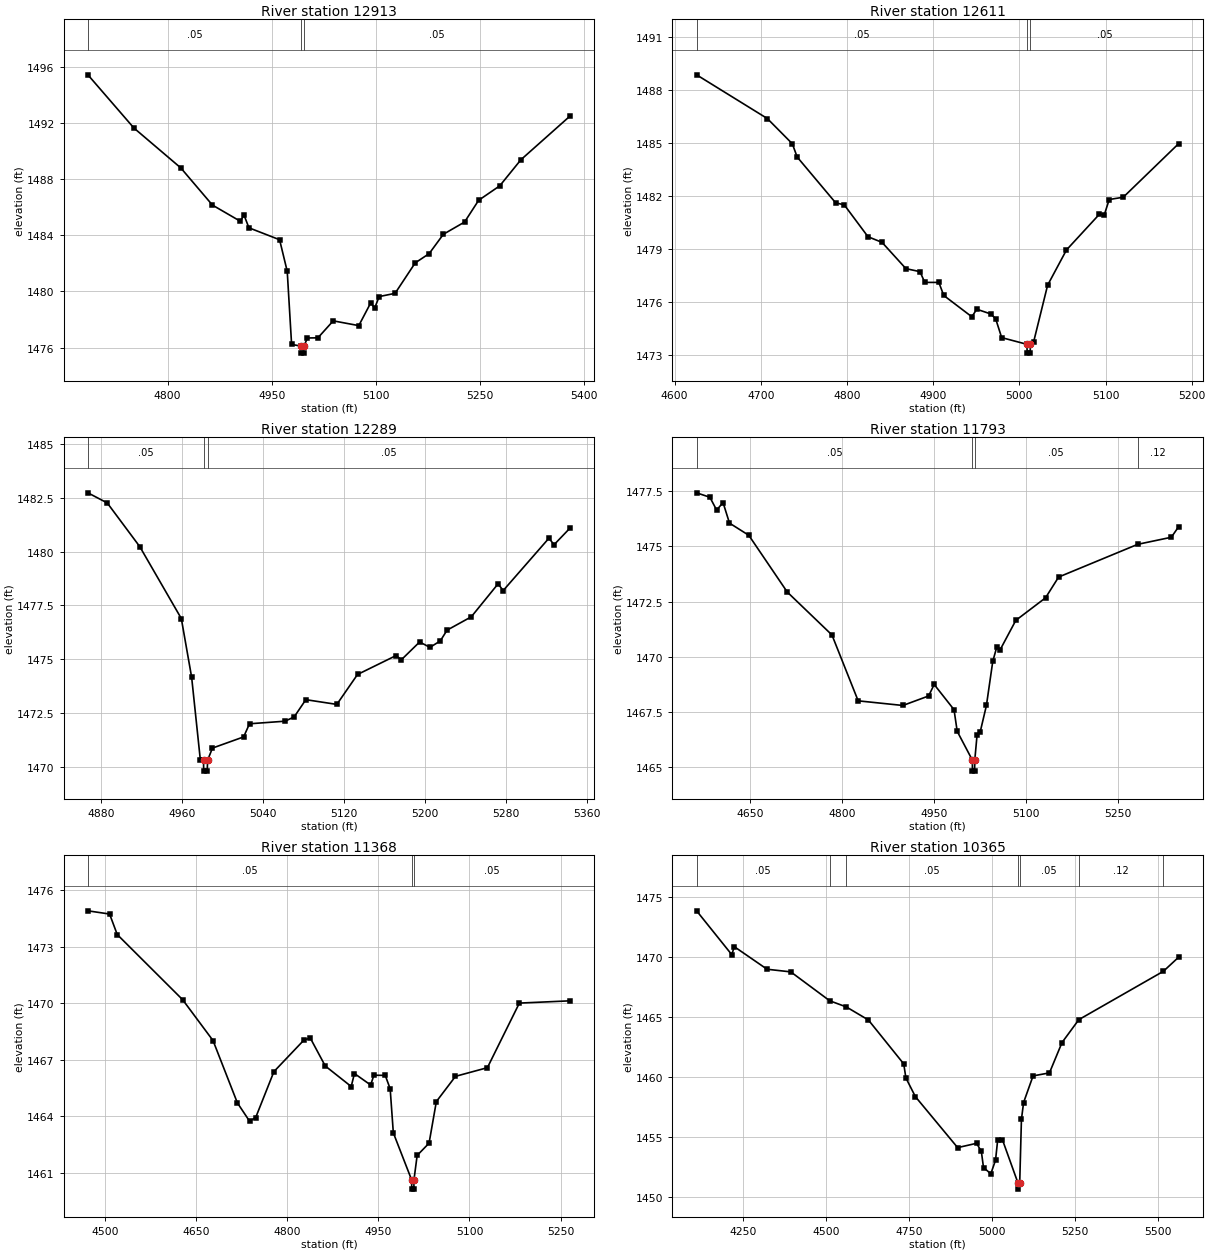
Type RM Length L Ch R = 1 ,12913   ,302,302,302
BEGIN DESCRIPTION:
SOUTH HELMS CREEK 26.0
END DESCRIPTION:
XS GIS Cut Line= 3
      2766955.69      10162653.1      2767139.66     10162261.03
      2767185.02     10162003.48
#Sta/Elev= 30
  4685.1 1495.43  4751.4 1491.64  4818.9  1488.8  4864.5 1486.15  4904.6    1485
  4910.1 1485.43  4917.1 1484.53  4961.3 1483.68  4972.3 1481.43  4978.6 1476.22
  4992.4  1476.1  4992.6  1475.6  4996.1  1475.6  4996.4  1476.1  5001.4 1476.68
  5016.5 1476.69  5038.6  1477.9  5075.4 1477.56  5092.7 1479.19  5098.2  1478.8
  5104.8 1479.63  5127.7 1479.86  5156.7 1482.03  5176.8 1482.69  5197.3 1484.07
  5227.8 1484.94  5248.1 1486.49  5278.5 1487.52    5309 1489.38  5379.7 1492.49
#Mann= 3 ,-1 , 0
  4685.1     .05       0  4992.4     .03       0  4996.4     .05       0
Bank Sta=4992.4,4996.4
XS Rating Curve= 0 ,0
Exp/Cntr=0.3,0.1

Type RM Length L Ch R = 1 ,12611   ,322,322,322
BEGIN DESCRIPTION:
Mapping XS d853a1ed
END DESCRIPTION:
XS GIS Cut Line= 2
      2767198.18      10162695.6      2767461.12     10162201.85
#Sta/Elev= 30
  4625.5 1488.87  4707.6 1486.39  4736.6 1484.96  4742.2 1484.21  4786.9 1481.61
  4796.8  1481.5  4824.4 1479.69  4840.7 1479.37  4868.4 1477.88  4884.7 1477.71
  4890.3  1477.1  4906.6  1477.1  4912.3 1476.36  4944.9 1475.15  4950.6 1475.58
  4966.9 1475.31  4972.5 1475.04  4979.5 1473.97  5008.8 1473.59  5009.1 1473.09
  5012.6 1473.09  5012.8 1473.59  5016.5 1473.71  5032.8 1476.94  5054.7 1478.94
  5092.8 1480.96  5098.7 1480.95  5104.3  1481.8  5120.6 1481.93  5184.9 1484.97
#Mann= 3 ,-1 , 0
  4625.5     .05       0  5008.8     .03       0  5012.8     .05       0
Bank Sta=5008.8,5012.8
XS Rating Curve= 0 ,0
Exp/Cntr=0.3,0.1

Type RM Length L Ch R = 1 ,12289   ,496,496,496
BEGIN DESCRIPTION:
SOUTH HELMS CREEK 25.0
END DESCRIPTION:
XS GIS Cut Line= 3
      2767505.69     10162753.07      2767546.42     10162571.22
      2767604.87     10162287.74
#Sta/Elev= 30
    4867 1482.73  4886.1 1482.26  4918.2 1480.23  4959.2 1476.89  4969.4 1474.16
    4978 1470.31  4981.1  1470.3  4981.3  1469.8  4984.8  1469.8  4985.1  1470.3
  4989.9 1470.87  5020.7 1471.39  5026.5    1472  5061.6 1472.12  5070.6 1472.32
  5082.1 1473.12  5112.7  1472.9  5133.1 1474.29  5171.2 1475.17  5176.3 1474.97
  5194.4  1475.8  5204.6 1475.55  5214.8 1475.85  5221.5 1476.35  5245.4 1476.97
  5271.8  1478.5  5276.9 1478.19    5322 1480.62  5327.1 1480.32  5342.8 1481.09
#Mann= 3 ,-1 , 0
    4867     .05       0  4981.1     .03       0  4985.1     .05       0
Bank Sta=4981.1,4985.1
XS Rating Curve= 0 ,0
Exp/Cntr=0.3,0.1

Type RM Length L Ch R = 1 ,11793   ,425,425,425
BEGIN DESCRIPTION:
SOUTH HELMS CREEK 24.0
END DESCRIPTION:
XS GIS Cut Line= 3
      2767812.71     10163064.32      2767969.87     10162566.53
       2767786.4     10162375.19
#Sta/Elev= 30
  4562.3 1477.42    4584 1477.22    4595 1476.64  4605.5 1476.98    4616 1476.05
  4647.5  1475.5  4710.4 1472.93  4783.3 1470.99  4826.1 1468.01  4899.1  1467.8
  4941.1 1468.23  4950.2 1468.75  4982.6 1467.61  4987.8 1466.63  5012.5 1465.33
  5012.7 1464.83  5016.2 1464.83  5016.5 1465.33  5020.2 1466.46  5025.4 1466.61
  5035.5  1467.8  5045.9  1469.8  5052.5 1470.45  5057.7 1470.31  5083.5 1471.65
    5132 1472.67  5153.4 1473.61  5282.5 1475.09  5337.4 1475.41  5349.4 1475.89
#Mann= 4 ,-1 , 0
  4562.3     .05       0  5012.5     .05       0  5016.5     .05       0
  5282.5     .12       0
Bank Sta=5012.5,5016.5
XS Rating Curve= 0 ,0
Exp/Cntr=0.3,0.1

Type RM Length L Ch R = 1 ,11368   ,1003,1003,1003
BEGIN DESCRIPTION:
SOUTH HELMS CREEK 23.0
END DESCRIPTION:
XS GIS Cut Line= 3
      2768158.02     10163248.71      2768182.89     10162821.42
      2768070.45     10162473.87
#Sta/Elev= 30
  4472.1  1474.9  4507.8 1474.73  4520.4 1473.64    4628 1470.18    4678 1468.01
  4718.1  1464.7  4738.1 1463.73  4748.2 1463.92  4778.2 1466.36  4828.3 1468.06
  4838.3 1468.13  4862.7 1466.66  4905.4 1465.57  4910.7 1466.26  4937.4 1465.65
  4942.7 1466.17  4961.4 1466.16  4969.5 1465.45  4974.7 1463.11  5004.7 1460.62
    5005 1460.12  5008.5 1460.12  5008.7 1460.62  5013.9 1461.91  5033.5 1462.56
  5045.5 1464.77    5077 1466.11  5129.5 1466.57  5182.1    1470  5265.4 1470.12
#Mann= 3 ,-1 , 0
  4472.1     .05       0  5004.7     .05       0  5008.7     .05       0
Bank Sta=5004.7,5008.7
XS Rating Curve= 0 ,0
Exp/Cntr=0.3,0.1

Type RM Length L Ch R = 1 ,10365   ,340,340,340
BEGIN DESCRIPTION:
SOUTH HELMS CREEK 21.0
END DESCRIPTION:
XS GIS Cut Line= 3
      2768205.67     10163503.12      2768895.45     10162685.35
      2768855.69     10162303.15
#Sta/Elev= 30
  4108.7 1473.82  4214.7 1470.17  4222.5 1470.83  4321.3 1468.95  4392.8 1468.73
  4510.3 1466.32  4560.3 1465.81  4626.9 1464.72  4733.5 1461.06    4740 1459.89
  4768.6 1458.33  4896.1 1454.08  4953.3 1454.44  4967.6 1453.76  4974.1 1452.42
  4996.2  1451.9  5010.4 1453.04    5017 1454.75  5031.3 1454.73  5078.2 1451.12
  5078.5 1450.62  5083.3 1451.12  5088.5 1456.43    5095 1457.84  5123.6 1460.06
    5173 1460.31  5210.9 1462.84  5261.7 1464.75  5516.7 1468.78  5562.8 1469.96
#Mann= 7 ,-1 , 0
  4108.7     .05       0  4510.3     .12       0  4560.3     .05       0
  5078.2     .05       0  5083.3     .05       0  5261.7     .12       0
  5516.7     .05       0
Bank Sta=5078.2,5083.3
XS Rating Curve= 0 ,0
Exp/Cntr=0.3,0.1

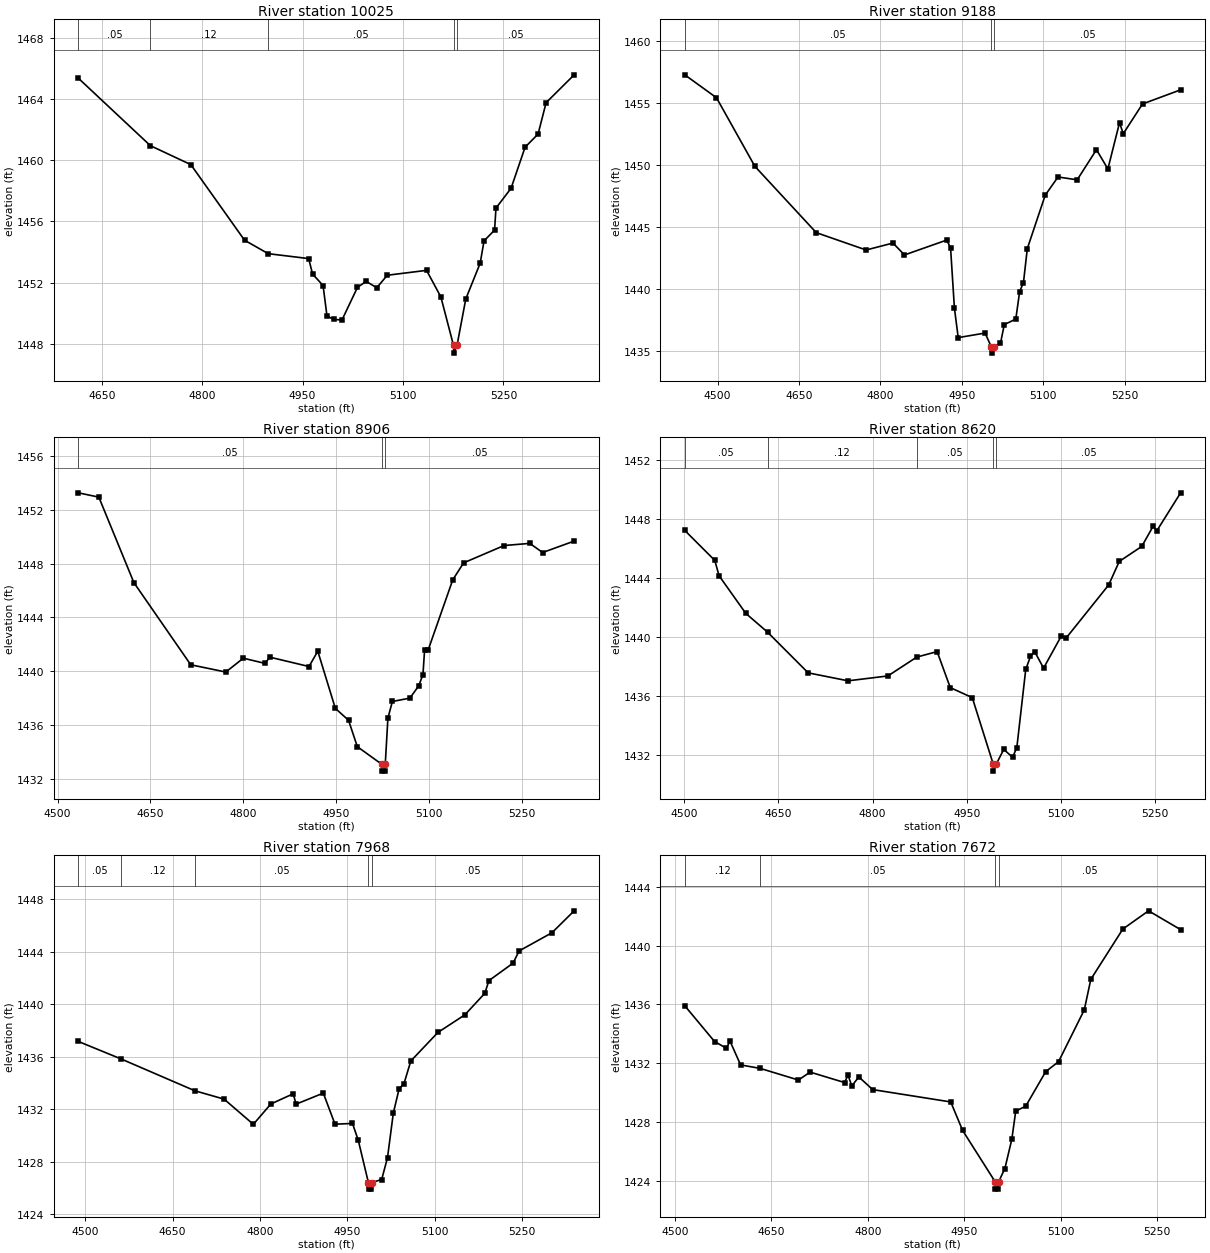
Type RM Length L Ch R = 1 ,10025   ,837,837,837
BEGIN DESCRIPTION:
SOUTH HELMS CREEK 20.0
END DESCRIPTION:
XS GIS Cut Line= 3
       2768705.7     10163453.09      2769020.79     10162914.47
      2769055.68     10162803.12
#Sta/Elev= 30
    4615 1465.36  4722.6 1460.95  4783.1 1459.71  4863.3 1454.77  4898.7 1453.89
  4959.1 1453.57  4964.9 1452.56  4980.6 1451.81  4986.4 1449.83  4996.3 1449.59
  5008.9 1449.56    5032 1451.69  5045.1 1452.08  5060.8 1451.66  5076.5 1452.48
  5135.2  1452.8  5156.6 1451.06  5175.5 1447.89  5175.9 1447.39  5180.7 1447.89
  5193.8 1450.93  5215.3 1453.27  5221.1 1454.73  5236.8 1455.43  5238.9 1456.87
  5261.4 1458.16  5282.4 1460.85  5301.8 1461.71  5313.8 1463.76  5355.7 1465.58
#Mann= 5 ,-1 , 0
    4615     .05       0  4722.6     .12       0  4898.7     .05       0
  5175.5     .05       0  5180.7     .05       0
Bank Sta=5175.5,5180.7
XS Rating Curve= 0 ,0
Exp/Cntr=0.3,0.1

Type RM Length L Ch R = 1 ,9188    ,282,282,282
BEGIN DESCRIPTION:
SOUTH HELMS CREEK 19.0
END DESCRIPTION:
XS GIS Cut Line= 3
      2769106.17     10163806.12      2769577.29     10163334.99
       2769755.8      10163163.8
#Sta/Elev= 30
  4439.5 1457.24  4497.9 1455.39  4568.6 1449.86  4681.7 1444.51  4773.6 1443.11
  4823.1 1443.67  4844.3 1442.71  4922.1 1443.91  4929.2 1443.28  4936.3 1438.41
  4943.3 1436.04  4992.8 1436.41  5004.3 1435.29  5004.8 1434.79  5009.6 1435.29
  5021.1 1435.57  5028.2 1437.09  5049.4 1437.54  5056.5 1439.76  5063.5 1440.48
  5070.6 1443.22  5103.6 1447.53  5127.2    1449  5162.5 1448.77    5198  1451.2
  5219.1 1449.65  5240.5 1453.38  5247.4 1452.49  5282.9 1454.89  5353.1 1456.03
#Mann= 3 ,-1 , 0
  4439.5     .05       0  5004.3     .03       0  5009.6     .05       0
Bank Sta=5004.3,5009.6
XS Rating Curve= 0 ,0
Exp/Cntr=0.3,0.1

Type RM Length L Ch R = 1 ,8906    ,286,286,286
BEGIN DESCRIPTION:
SOUTH HELMS CREEK 18.0
END DESCRIPTION:
XS GIS Cut Line= 3
      2769356.36      10163930.5      2769744.23     10163524.94
      2769807.01       10163294.
#Sta/Elev= 30
  4533.5 1453.26  4566.6 1452.94  4623.2 1446.58    4715 1440.47  4771.6 1439.93
  4799.9 1440.96  4835.2 1440.57  4842.4 1441.04  4905.9 1440.34  4920.1 1441.48
  4948.4 1437.23  4969.8 1436.34  4983.9 1434.38  5023.7 1433.06  5024.2 1432.56
  5028.6 1432.56    5029 1433.06  5033.3  1436.5  5040.5 1437.74  5068.8 1437.99
    5083  1438.9  5089.9 1439.74  5092.5 1441.56  5098.2 1441.56    5138 1446.79
  5155.5 1448.05  5220.9 1449.34  5262.4  1449.5  5283.1 1448.82    5334 1449.67
#Mann= 3 ,-1 , 0
  4533.5     .05       0  5023.7     .05       0    5029     .05       0
Bank Sta=5023.7,5029
XS Rating Curve= 0 ,0
Exp/Cntr=0.3,0.1

Type RM Length L Ch R = 1 ,8620    ,652,652,652
BEGIN DESCRIPTION:
SOUTH HELMS CREEK 17.0
END DESCRIPTION:
XS GIS Cut Line= 3
      2769577.31     10164122.16      2769984.05     10163671.52
       2770055.7     10163503.08
#Sta/Elev= 30
  4500.7 1447.25  4548.5 1445.22  4555.3 1444.18  4597.9 1441.63  4632.5 1440.36
  4697.3  1437.6  4760.8 1437.06  4824.3 1437.39  4870.4 1438.67  4902.8 1439.04
  4923.7  1436.6  4958.8 1435.92    4992 1431.44  4992.4 1430.94  4997.3 1431.44
  5008.9 1432.41  5023.1 1431.88  5029.8 1432.54    5044 1437.83  5051.5 1438.71
  5058.2 1439.04  5072.4 1437.92  5100.8 1440.11  5107.8 1439.93  5176.2 1443.56
    5193 1445.15  5228.9 1446.17  5247.2 1447.55  5252.6 1447.21  5290.8  1449.8
#Mann= 5 ,-1 , 0
  4500.7     .05       0  4632.5     .12       0  4870.4     .05       0
    4992     .05       0  4997.3     .05       0
Bank Sta=4992,4997.3
XS Rating Curve= 0 ,0
Exp/Cntr=0.3,0.1

Type RM Length L Ch R = 1 ,7968    ,296,296,296
BEGIN DESCRIPTION:
SOUTH HELMS CREEK 16.0
END DESCRIPTION:
XS GIS Cut Line= 3
      2770281.07     10164523.06       2770311.8     10163940.74
      2770380.57     10163681.75
#Sta/Elev= 30
  4488.1 1437.16  4561.8 1435.82  4688.1  1433.4  4738.4 1432.76  4788.5 1430.84
  4818.5 1432.39  4856.9 1433.17  4861.9 1432.38  4908.6 1433.22  4928.7 1430.85
  4958.7 1430.91  4968.7 1429.61    4986  1426.4  4986.5  1425.9    4991  1425.9
  4991.4  1426.4  5008.8 1426.63  5018.8  1428.3  5028.8  1431.7  5038.8 1433.56
    5047 1433.93  5058.8 1435.67  5105.4 1437.85  5151.6 1439.19  5185.8 1440.83
  5192.9  1441.8  5234.3 1443.13  5244.7 1444.06  5301.1 1445.45  5339.2 1447.12
#Mann= 5 ,-1 , 0
  4488.1     .05       0  4561.8     .12       0  4688.1     .05       0
    4986     .03       0  4991.4     .05       0
Bank Sta=4986,4991.4
XS Rating Curve= 0 ,0
Exp/Cntr=0.3,0.1

Type RM Length L Ch R = 1 ,7672    ,312,312,312
BEGIN DESCRIPTION:
Mapping XS 66779cd5
END DESCRIPTION:
XS GIS Cut Line= 3
      2770403.99      10164533.3      2770611.75       10164030.
      2770608.82     10163803.21
#Sta/Elev= 30
  4515.3 1435.91  4561.6 1433.48  4580.1 1433.02  4585.5 1433.52  4602.1 1431.89
  4632.8 1431.65  4692.1 1430.86  4710.2  1431.4  4763.8 1430.69  4769.2 1431.19
  4775.1 1430.46    4786 1431.07  4807.6 1430.21    4929 1429.37  4947.5 1427.43
  4998.1 1423.94  4998.5 1423.44  5003.1 1423.44  5003.5 1423.94  5013.2 1424.84
    5024 1426.83  5030.1 1428.75  5045.6 1429.08  5076.7 1431.43  5096.7 1432.11
  5136.7 1435.63  5146.9 1437.71  5196.7 1441.13  5236.7 1442.37  5286.6 1441.09
#Mann= 4 ,-1 , 0
  4515.3     .12       0  4632.8     .05       0  4998.1     .03       0
  5003.5     .05       0
Bank Sta=4998.1,5003.5
XS Rating Curve= 0 ,0
Exp/Cntr=0.3,0.1

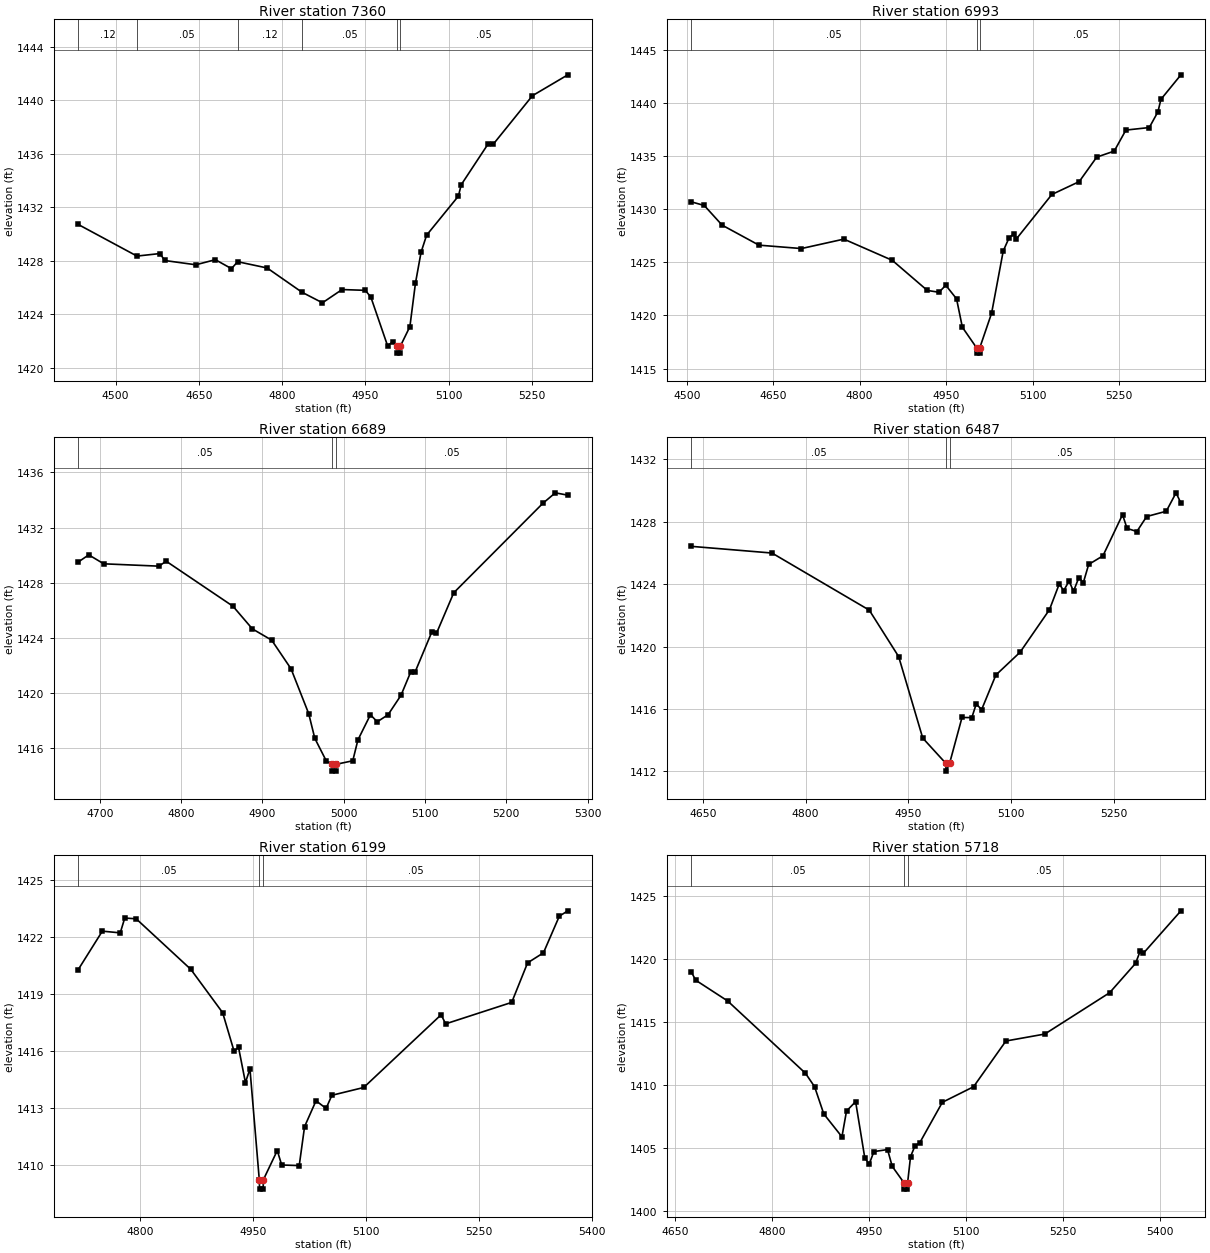
Type RM Length L Ch R = 1 ,7360    ,367,367,367
BEGIN DESCRIPTION:
SOUTH HELMS CREEK 15.0
END DESCRIPTION:
XS GIS Cut Line= 3
      2770582.49     10164607.94       2770883.9     10164217.28
      2770917.55     10163829.56
#Sta/Elev= 30
  4432.2 1430.72  4538.4 1428.35  4580.1 1428.54  4588.2 1428.02  4644.4  1427.7
  4679.7 1428.08  4708.7 1427.41  4719.8 1427.93    4773 1427.46  4835.7 1425.65
  4872.6 1424.86    4908 1425.85  4949.9 1425.79  4959.9 1425.28    4990 1421.65
  4999.6 1421.96  5007.4  1421.6  5007.8  1421.1  5012.4  1421.1  5012.8  1421.6
  5030.2 1423.08  5040.2 1426.32  5050.3 1428.63  5060.3 1429.91  5117.6 1432.83
  5122.7 1433.68  5170.7  1436.7  5180.7 1436.72    5251 1440.33  5314.8 1441.89
#Mann= 6 ,-1 , 0
  4432.2     .12       0  4538.4     .05       0  4719.8     .12       0
  4835.7     .05       0  5007.4     .03       0  5012.8     .05       0
Bank Sta=5007.4,5012.8
XS Rating Curve= 0 ,0
Exp/Cntr=0.3,0.1

Type RM Length L Ch R = 1 ,6993    ,304,304,304
BEGIN DESCRIPTION:
Mapping XS b4404da9
END DESCRIPTION:
XS GIS Cut Line= 3
      2770731.75     10164672.29      2770876.58     10164433.83
      2771439.89     10164341.65
#Sta/Elev= 30
  4507.7 1430.72  4530.5 1430.37  4561.4 1428.52  4625.4 1426.63    4699 1426.31
  4772.7  1427.2  4856.7  1425.2  4917.5 1422.36  4937.8 1422.19  4949.5 1422.85
  4968.2 1421.57  4978.3 1418.89    5003 1416.95  5003.5 1416.45  5008.1 1416.45
  5008.5 1416.95    5029 1420.21  5049.2 1426.08  5059.4 1427.33  5067.1 1427.67
  5072.2 1427.23  5133.6 1431.41    5181 1432.62  5211.4 1434.93  5241.8  1435.5
    5262 1437.48  5302.6 1437.72  5317.6  1439.2  5322.8 1440.38  5357.5 1442.69
#Mann= 3 ,-1 , 0
  4507.7     .05       0    5003     .05       0  5008.5     .05       0
Bank Sta=5003,5008.5
XS Rating Curve= 0 ,0
Exp/Cntr=0.3,0.1

Type RM Length L Ch R = 1 ,6689    ,202,202,202
BEGIN DESCRIPTION:
SOUTH HELMS CREEK 14.0
END DESCRIPTION:
XS GIS Cut Line= 3
      2770883.94     10164811.31      2771261.79     10164653.18
      2771425.23     10164550.91
#Sta/Elev= 30
  4673.3 1429.49  4686.5 1430.02  4704.9 1429.37  4772.8  1429.2  4781.7 1429.56
  4863.9 1426.29  4887.7 1424.65  4911.5 1423.83  4935.3 1421.75    4957  1418.5
  4964.5 1416.71  4978.7 1415.06  4985.5 1414.83    4986 1414.33  4990.6 1414.33
    4991 1414.83  5011.2 1415.08  5017.5 1416.59  5032.9 1418.42  5041.3 1417.91
  5054.6 1418.42  5070.5 1419.83  5082.3  1421.5  5087.7  1421.5  5108.3 1424.41
  5114.1 1424.32  5135.4 1427.27    5245 1433.76  5260.3 1434.52  5275.7 1434.35
#Mann= 3 ,-1 , 0
  4673.3     .05       0  4985.5     .05       0    4991     .05       0
Bank Sta=4985.5,4991
XS Rating Curve= 0 ,0
Exp/Cntr=0.3,0.1

Type RM Length L Ch R = 1 ,6487    ,288,288,288
BEGIN DESCRIPTION:
SOUTH HELMS CREEK 13.0
END DESCRIPTION:
XS GIS Cut Line= 3
      2771008.23     10165092.28      2771360.89      10164796.7
      2771524.79     10164602.06
#Sta/Elev= 30
    4633 1426.43    4751    1426  4892.9 1422.34  4935.8 1419.36  4970.9 1414.14
  5004.6 1412.52    5005 1412.02  5010.1 1412.52  5028.2 1415.46  5042.5 1415.45
    5049 1416.33  5056.8 1415.96  5077.6 1418.18  5112.9 1419.64  5155.8 1422.37
  5170.1 1424.02  5176.6 1423.59  5184.4 1424.21  5190.9 1423.55  5198.7 1424.43
  5205.2  1424.1    5213 1425.27  5233.8 1425.82  5262.4 1428.46    5269 1427.58
  5283.3 1427.38  5297.6 1428.34  5326.2 1428.68  5340.5 1429.86  5347.6  1429.2
#Mann= 3 ,-1 , 0
    4633     .05       0  5004.6     .05       0  5010.1     .05       0
Bank Sta=5004.6,5010.1
XS Rating Curve= 0 ,0
Exp/Cntr=0.3,0.1

Type RM Length L Ch R = 1 ,6199    ,481,481,481
BEGIN DESCRIPTION:
Mapping XS 0faa5963
END DESCRIPTION:
XS GIS Cut Line= 2
      2771376.99     10165250.27      2771729.61     10164703.04
#Sta/Elev= 30
  4717.1 1420.27  4749.4 1422.31  4773.2 1422.22  4779.2    1423  4794.4 1422.96
    4867  1420.3  4909.3 1418.02  4924.5 1415.99  4930.4  1416.2  4939.6 1414.34
  4945.6 1415.06    4958 1409.23  4958.4 1408.73  4963.1 1408.73  4963.5 1409.23
  4981.9 1410.76  4987.8    1410  5011.1 1409.97  5018.2 1412.02  5033.4 1413.38
  5046.8 1412.98  5054.5 1413.67  5096.8 1414.08  5199.7 1417.91  5205.7 1417.43
  5293.5 1418.56  5314.6 1420.64  5335.7 1421.17  5356.8  1423.1  5368.1 1423.38
#Mann= 3 ,-1 , 0
  4717.1     .05       0    4958     .03       0  4963.5     .05       0
Bank Sta=4958,4963.5
XS Rating Curve= 0 ,0
Exp/Cntr=0.3,0.1

Type RM Length L Ch R = 1 ,5718    ,381,381,381
BEGIN DESCRIPTION:
SOUTH HELMS CREEK 12.0
END DESCRIPTION:
XS GIS Cut Line= 3
      2771655.67     10165553.13      2771925.67     10165266.37
      2771955.69     10164903.07
#Sta/Elev= 30
  4674.5 1418.98  4681.6  1418.3    4731 1416.66  4851.5 1410.94  4865.7 1409.87
  4879.9 1407.72    4908 1405.91  4915.1 1407.95  4929.2 1408.69  4943.4 1404.24
  4950.2 1403.75  4957.5 1404.74  4978.6  1404.9  4985.9 1403.57  5004.1 1402.27
  5004.5 1401.77  5009.2 1401.77  5009.7 1402.27  5014.2 1404.33    5021 1405.18
  5028.3 1405.42  5063.5 1408.64  5111.8 1409.87  5161.9 1413.49  5222.1 1414.04
  5322.5 1417.31  5362.6 1419.63  5369.9 1420.61  5374.9 1420.44  5432.9 1423.79
#Mann= 3 ,-1 , 0
  4674.5     .05       0  5004.1     .05       0  5009.7     .05       0
Bank Sta=5004.1,5009.7
XS Rating Curve= 0 ,0
Exp/Cntr=0.3,0.1

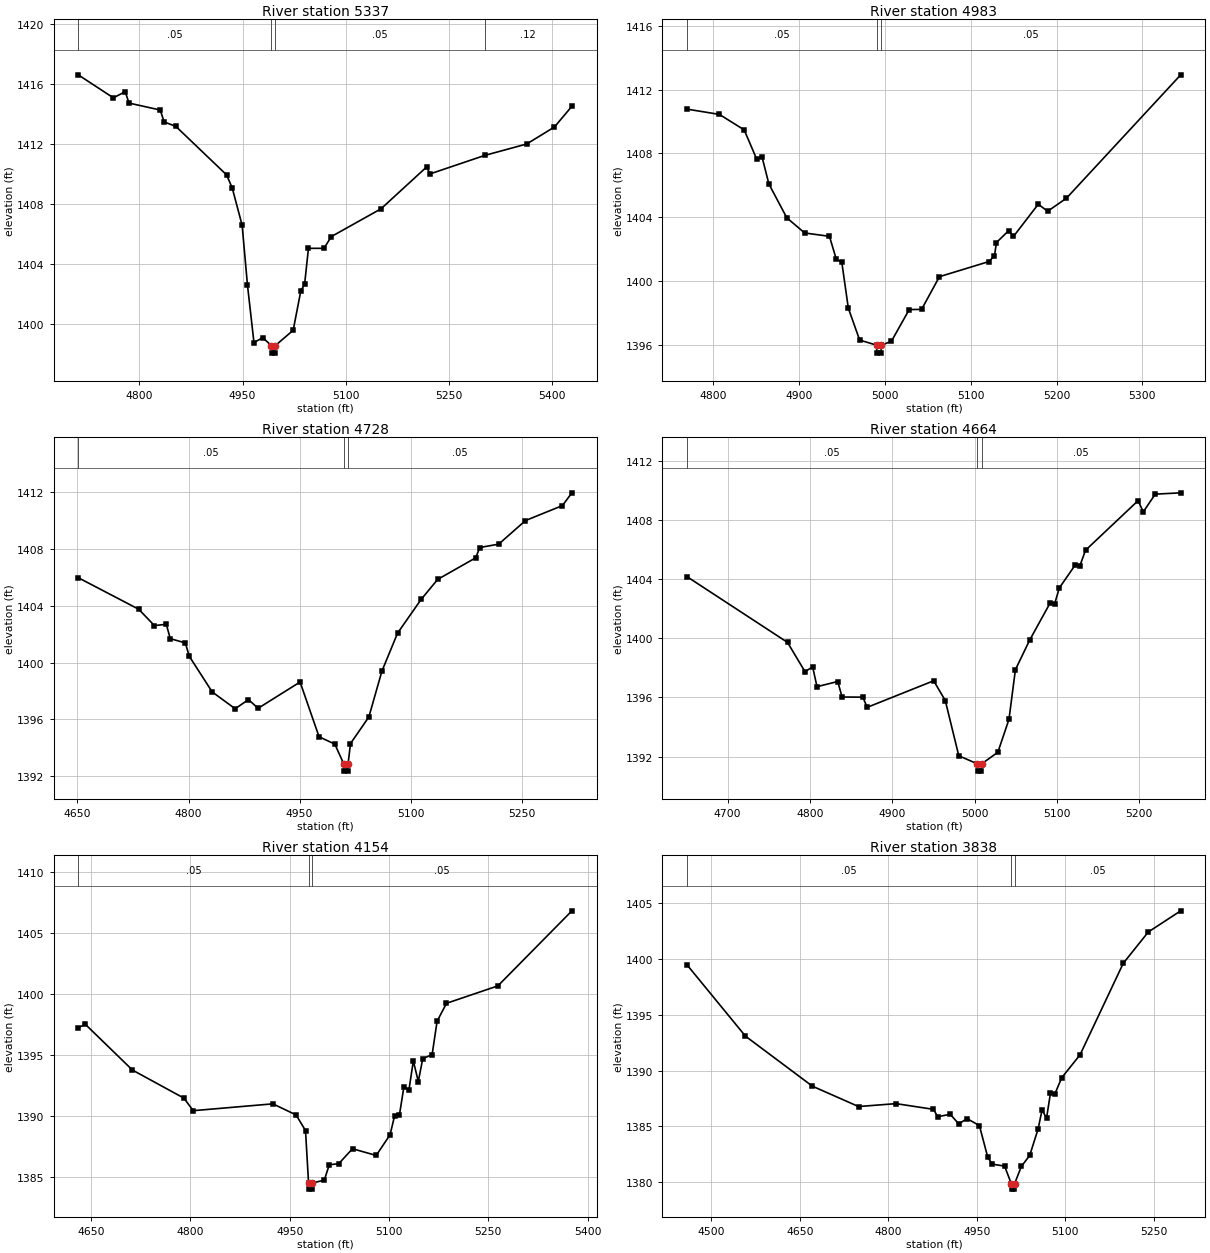
Type RM Length L Ch R = 1 ,5337    ,354,354,354
BEGIN DESCRIPTION:
SOUTH HELMS CREEK 11.0
END DESCRIPTION:
XS GIS Cut Line= 3
      2772069.05     10165755.09      2772235.86     10165405.37
       2772276.8     10165077.88
#Sta/Elev= 30
  4711.2  1416.6  4762.3 1415.07  4779.5 1415.48    4785 1414.72  4830.4 1414.26
    4836 1413.47  4853.1 1413.17  4926.7 1409.95    4935 1409.08  4949.4  1406.6
  4957.1 1402.65  4966.6 1398.79  4979.3 1399.12    4992 1398.59  4992.5 1398.09
  4997.2 1398.09  4997.6 1398.59  5023.6 1399.61  5034.7 1402.23  5040.2 1402.67
  5045.8 1405.06  5068.4 1405.06    5079 1405.84  5151.3 1407.69  5217.5 1410.47
  5222.5 1410.01    5302 1411.24    5363    1412  5403.3 1413.13  5428.7 1414.51
#Mann= 4 ,-1 , 0
  4711.2     .05       0    4992     .03       0  4997.6     .05       0
    5302     .12       0
Bank Sta=4992,4997.6
XS Rating Curve= 0 ,0
Exp/Cntr=0.3,0.1

Type RM Length L Ch R = 1 ,4983    ,255,255,255
BEGIN DESCRIPTION:
SOUTH HELMS CREEK 10.0
END DESCRIPTION:
XS GIS Cut Line= 3
      2772339.72     10165870.69      2772563.61      10165586.8
      2772651.04     10165391.54
#Sta/Elev= 30
  4769.2 1410.77  4806.9 1410.44  4835.8 1409.47  4850.2 1407.66  4856.6 1407.78
  4864.6 1406.08  4885.5 1403.96  4906.3 1403.01  4935.2  1402.8  4943.2 1401.36
  4949.6 1401.18  4957.2  1398.3  4970.4  1396.3  4990.1 1395.98  4990.5 1395.48
  4995.3 1395.48  4995.8 1395.98  5007.4 1396.22  5028.2 1398.21  5042.6 1398.22
  5063.4 1400.27  5121.2 1401.22  5127.6 1401.59  5129.9 1402.41  5144.2 1403.16
  5149.7 1402.79  5178.6 1404.81  5189.6 1404.37  5211.5 1405.19  5344.7 1412.92
#Mann= 3 ,-1 , 0
  4769.2     .05       0  4990.1     .03       0  4995.8     .05       0
Bank Sta=4990.1,4995.8
XS Rating Curve= 0 ,0
Exp/Cntr=0.3,0.1

Type RM Length L Ch R = 1 ,4728    ,64,64,64
BEGIN DESCRIPTION:
Mapping XS 8dac30e5
END DESCRIPTION:
XS GIS Cut Line= 2
      2772581.16     10166150.15      2772802.12     10165520.92
#Sta/Elev= 30
    4651 1405.97  4732.7 1403.75  4753.9  1402.6    4770 1402.69  4775.3 1401.68
  4795.7 1401.38    4801 1400.44    4832 1397.93    4863 1396.75    4881 1397.39
    4894 1396.78  4950.7 1398.63  4976.3 1394.78  4997.6 1394.26  5009.8 1392.86
  5010.2 1392.36    5015 1392.36  5015.5 1392.86  5018.8  1394.3  5043.6 1396.17
  5061.2 1399.39  5082.4 1402.07  5114.2 1404.44  5136.6 1405.85    5188 1407.37
  5193.3 1408.09    5219 1408.33  5255.2 1409.99    5305 1411.04  5317.9 1411.94
#Mann= 3 ,-1 , 0
    4651     .05       0  5009.8     .05       0  5015.5     .05       0
Bank Sta=5009.8,5015.5
XS Rating Curve= 0 ,0
Exp/Cntr=0.3,0.1

Type RM Length L Ch R = 1 ,4664    ,510,510,510
BEGIN DESCRIPTION:
SOUTH HELMS CREEK 9.0
END DESCRIPTION:
XS GIS Cut Line= 3
      2772636.76      10166167.7      2772822.59     10165661.43
      2772859.18     10165613.12
#Sta/Elev= 30
  4650.7 1404.18  4772.8 1399.73  4794.1 1397.74  4803.3 1398.08  4808.6 1396.73
  4833.8 1397.08  4839.1 1396.03  4864.3 1396.02  4869.6 1395.33  4950.4 1397.13
  4964.5 1395.79  4980.9 1392.05  5003.2 1391.51  5003.7 1391.01  5008.5 1391.01
  5008.9 1391.51  5028.4 1392.29  5041.9 1394.52  5049.7 1397.88    5067 1399.88
  5092.2 1402.43  5097.5 1402.36    5103 1403.41  5122.7    1405    5128 1404.91
  5134.9 1405.97  5198.8 1409.33  5205.1 1408.57  5219.6 1409.77  5250.6 1409.86
#Mann= 3 ,-1 , 0
  4650.7     .05       0  5003.2     .05       0  5008.9     .05       0
Bank Sta=5003.2,5008.9
XS Rating Curve= 0 ,0
Exp/Cntr=0.3,0.1

Type RM Length L Ch R = 1 ,4154    ,316,316,316
BEGIN DESCRIPTION:
Mapping XS 6c3dcdd5
END DESCRIPTION:
XS GIS Cut Line= 2
      2772791.83     10166464.73      2773344.94      10165964.3
#Sta/Elev= 30
  4630.5 1397.27  4641.4 1397.53  4712.4 1393.79  4790.1 1391.49  4804.3 1390.46
  4924.6 1391.02  4959.7 1390.11  4973.9 1388.83  4978.5 1384.53    4979 1384.03
  4983.8 1384.03  4984.3 1384.53  5002.3 1384.77  5009.8 1386.03    5024 1386.11
  5044.9 1387.34  5080.7 1386.79  5101.7 1388.49  5108.4 1390.02  5115.9 1390.14
  5122.6 1392.43  5130.1 1392.13  5136.8 1394.54  5144.3 1392.85    5151 1394.72
  5165.2 1395.06  5172.7 1397.79  5186.9 1399.26  5264.6 1400.69  5376.4 1406.84
#Mann= 3 ,-1 , 0
  4630.5     .05       0  4978.5     .05       0  4984.3     .05       0
Bank Sta=4978.5,4984.3
XS Rating Curve= 0 ,0
Exp/Cntr=0.3,0.1

Type RM Length L Ch R = 1 ,3838    ,239,239,239
BEGIN DESCRIPTION:
SOUTH HELMS CREEK 8.0
END DESCRIPTION:
XS GIS Cut Line= 3
      2772905.71     10166753.09      2773387.37     10166331.56
      2773555.28     10166227.89
#Sta/Elev= 30
  4458.6 1399.44  4557.7 1393.07  4671.2  1388.6  4749.5 1386.78  4813.1 1387.04
  4876.6 1386.53  4883.8 1385.87  4905.1 1386.09  4919.4 1385.23  4933.6  1385.7
  4954.5 1385.08  4968.7 1382.24  4976.3 1381.63  4997.2 1381.46  5008.5  1379.9
    5009  1379.4  5013.8  1379.4  5014.3  1379.9  5025.7 1381.43  5039.9 1382.42
  5054.1 1384.78  5060.8 1386.48  5068.4 1385.74    5075 1387.97  5082.6 1387.92
  5094.2 1389.36  5125.2  1391.4  5198.5 1399.58    5241 1402.38    5296 1404.27
#Mann= 3 ,-1 , 0
  4458.6     .05       0  5008.5     .05       0  5014.3     .05       0
Bank Sta=5008.5,5014.3
XS Rating Curve= 0 ,0
Exp/Cntr=0.3,0.1