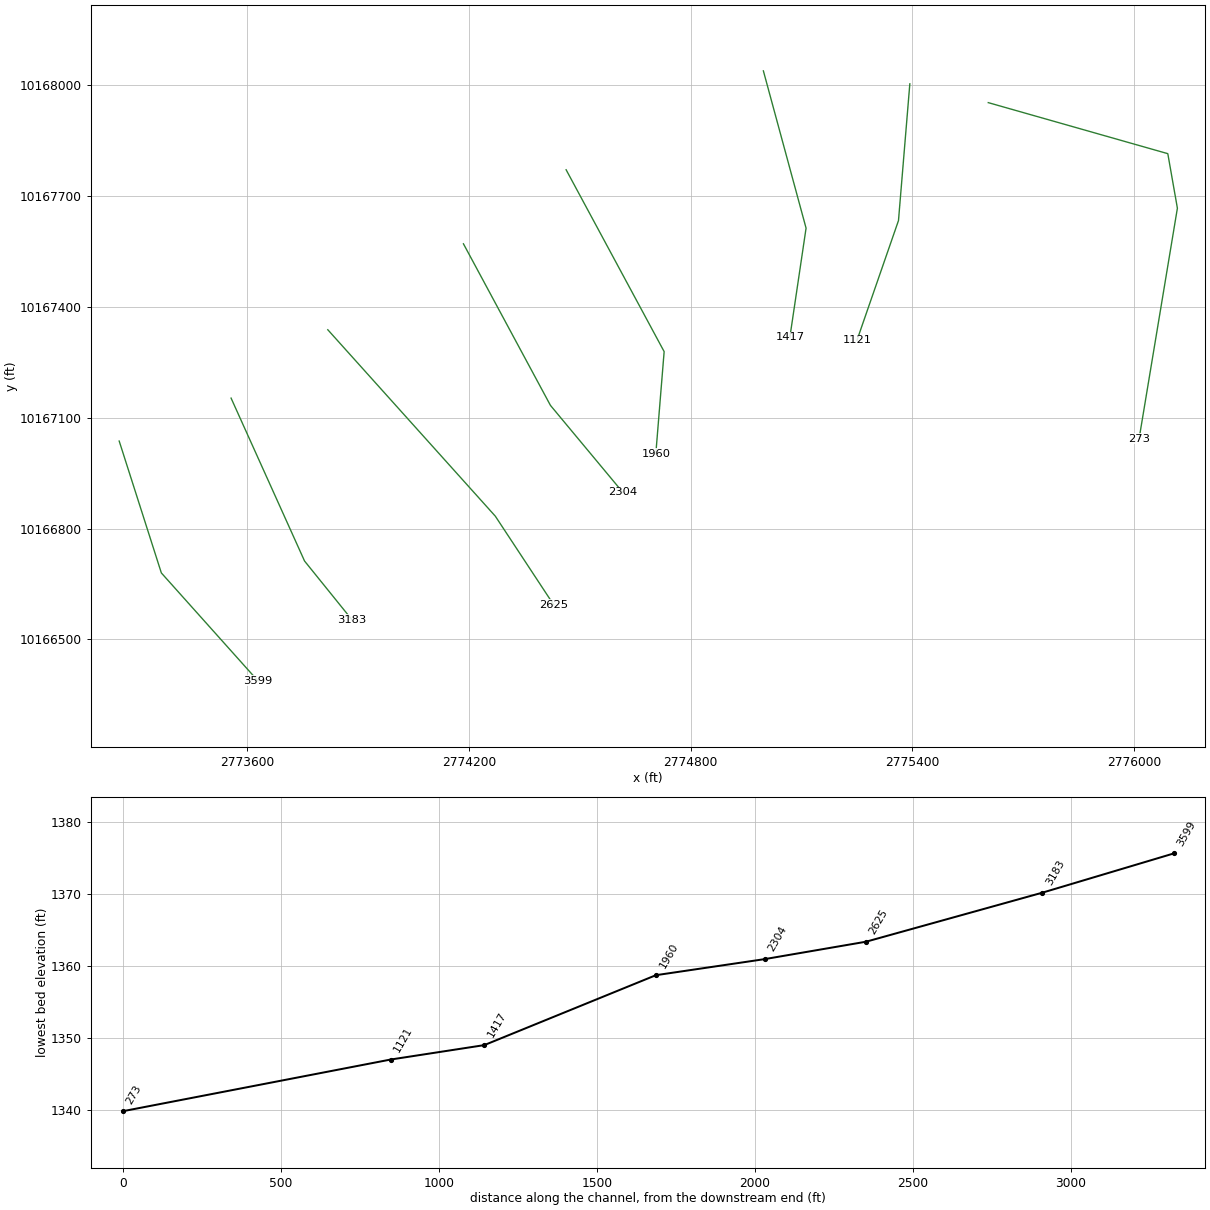
HEC-RAS study SOUTH HELMS CREEK.prj: SOUTH HELMS CREEK Base Level Engineering

--- SOUTH HELMS CREEK.g01 (geometry) --- (continued)

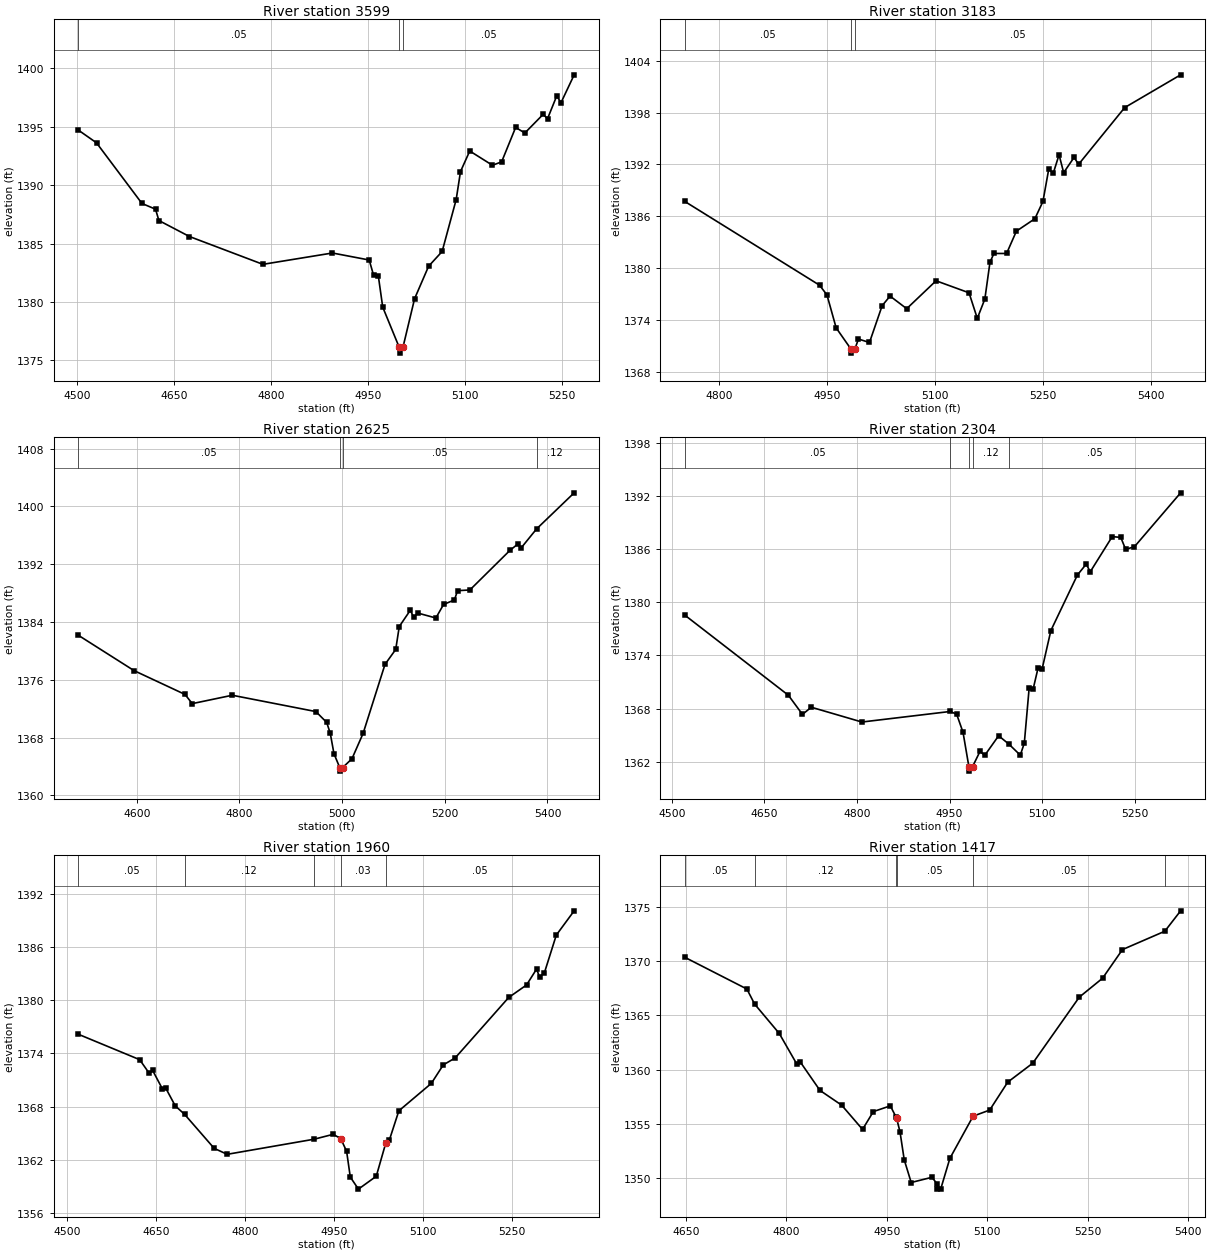
Type RM Length L Ch R = 1 ,3599    ,416,416,416
BEGIN DESCRIPTION:
SOUTH HELMS CREEK 7.0
END DESCRIPTION:
XS GIS Cut Line= 3
      2773252.75     10167036.84      2773366.89     10166679.79
      2773628.35     10166387.66
#Sta/Elev= 30
  4501.9 1394.71    4530 1393.62  4600.3 1388.43  4621.3 1387.94  4626.5 1386.97
  4673.8  1385.6  4787.4 1383.22  4894.9 1384.19  4951.8 1383.59  4958.5  1382.3
    4966 1382.19  4972.7 1379.56  4998.2 1376.12  4998.7 1375.62    5004 1376.12
    5022 1380.28  5043.7 1383.06  5064.6 1384.32  5086.3 1388.76    5093 1391.16
  5107.3 1392.92  5142.4  1391.7  5156.6 1391.99  5178.3 1394.94  5192.5 1394.46
  5220.9 1396.06  5227.6 1395.68  5241.8 1397.63  5248.5 1397.06  5268.8 1399.44
#Mann= 3 ,-1 , 0
  4501.9     .05       0  4998.2     .05       0    5004     .05       0
Bank Sta=4998.2,5004
XS Rating Curve= 0 ,0
Exp/Cntr=0.3,0.1

Type RM Length L Ch R = 1 ,3183    ,558,558,558
BEGIN DESCRIPTION:
SOUTH HELMS CREEK 6.0
END DESCRIPTION:
XS GIS Cut Line= 3
      2773555.68     10167153.11      2773754.63     10166711.98
      2773883.39     10166552.49
#Sta/Elev= 30
  4752.8 1387.72    4940 1378.03  4950.3 1376.91  4963.1 1373.09  4983.4 1370.67
  4983.8 1370.17  4989.2 1370.67  4994.1  1371.8  5009.4  1371.4    5027 1375.66
    5038 1376.77  5061.1 1375.31  5101.9 1378.54  5147.7 1377.15  5159.2 1374.19
  5169.7 1376.43  5176.8 1380.68  5182.3  1381.7  5199.9  1381.7  5213.5 1384.28
  5239.2 1385.72  5250.4 1387.72  5258.4 1391.43  5264.8    1391  5272.8 1393.12
  5279.2 1391.05  5293.6 1392.81    5300 1392.02    5364 1398.58  5441.7 1402.37
#Mann= 3 ,-1 , 0
  4752.8     .05       0  4983.4     .05       0  4989.2     .05       0
Bank Sta=4983.4,4989.2
XS Rating Curve= 0 ,0
Exp/Cntr=0.3,0.1

Type RM Length L Ch R = 1 ,2625    ,321,321,321
BEGIN DESCRIPTION:
SOUTH HELMS CREEK 5.0
END DESCRIPTION:
XS GIS Cut Line= 3
      2773817.57     10167338.18      2774271.12     10166833.42
      2774429.14     10166593.47
#Sta/Elev= 30
  4486.1 1382.16  4594.6 1377.27    4694 1373.97    4708  1372.7    4786 1373.86
  4948.9  1371.6  4969.9  1370.1  4976.9 1368.59  4984.1 1365.77  4995.3 1363.86
  4995.8 1363.36  5001.2 1363.86  5019.2 1365.08  5040.9 1368.59  5083.5 1378.13
  5104.4  1380.2  5111.3 1383.37  5132.8 1385.62  5139.5 1384.64    5147 1385.24
  5182.6 1384.55  5197.6 1386.42  5218.7 1387.05  5224.9 1388.33  5248.9 1388.43
  5327.1 1393.92  5342.2 1394.78  5348.2  1394.2  5378.7 1396.87    5452 1401.87
#Mann= 4 ,-1 , 0
  4486.1     .05       0  4995.3     .05       0  5001.2     .05       0
  5378.7     .12       0
Bank Sta=4995.3,5001.2
XS Rating Curve= 0 ,0
Exp/Cntr=0.3,0.1

Type RM Length L Ch R = 1 ,2304    ,344,344,344
BEGIN DESCRIPTION:
Mapping XS 0ed5a3d6
END DESCRIPTION:
XS GIS Cut Line= 3
      2774184.78     10167570.89      2774420.37     10167133.37
       2774616.3     10166897.95
#Sta/Elev= 30
  4521.2 1378.54    4689  1369.5  4711.8 1367.34  4726.1 1368.15  4808.1 1366.48
  4951.1 1367.67  4961.6 1367.36  4971.9 1365.32  4981.4 1361.44  4981.8 1360.94
  4987.3 1361.44  4999.5 1363.18    5007 1362.71  5029.6 1364.93  5046.3 1363.98
  5064.7 1362.74  5071.2 1364.11  5079.1 1370.37  5085.6 1370.23  5093.4 1372.56
  5099.9 1372.43  5114.2  1376.8  5157.2 1383.07  5171.5  1384.3    5178 1383.43
  5213.6  1387.4  5227.5 1387.31  5235.3 1385.96  5249.6 1386.26  5324.4 1392.34
#Mann= 5 ,-1 , 0
  4521.2     .05       0  4951.1     .12       0  4981.4     .05       0
  4987.3     .12       0  5046.3     .05       0
Bank Sta=4981.4,4987.3
XS Rating Curve= 0 ,0
Exp/Cntr=0.3,0.1

Type RM Length L Ch R = 1 ,1960    ,543,543,543
BEGIN DESCRIPTION:
SOUTH HELMS CREEK 4.0
END DESCRIPTION:
XS GIS Cut Line= 3
       2774462.8     10167771.31      2774728.18     10167279.01
      2774705.68      10167003.1
#Sta/Elev= 30
  4518.7 1376.15  4622.1 1373.29  4638.3 1371.75    4644 1372.08  4660.2 1370.03
  4665.9 1370.11  4682.1 1368.09  4697.9 1367.13  4747.8  1363.3  4769.7 1362.63
  4916.2 1364.33  4948.4 1364.88  4961.1 1364.41  4971.1 1362.97  4977.3 1360.07
    4991 1358.71  5021.1 1360.16  5037.3 1363.94    5043  1364.2  5059.2 1367.53
    5114 1370.62  5134.1  1372.7  5154.1 1373.48  5244.4 1380.29  5274.5  1381.7
  5291.4 1383.49  5296.4 1382.61  5304.6 1383.07  5324.7 1387.32  5354.8 1390.05
#Mann= 5 ,-1 , 0
  4518.7     .05       0  4697.9     .12       0  4916.2     .05       0
  4961.1     .03       0  5037.3     .05       0
Bank Sta=4961.1,5037.3
XS Rating Curve= 0 ,0
Exp/Cntr=0.3,0.1

Type RM Length L Ch R = 1 ,1417    ,296,296,296
BEGIN DESCRIPTION:
SOUTH HELMS CREEK 3.0
END DESCRIPTION:
XS GIS Cut Line= 3
      2774996.85     10168039.07      2775112.44     10167613.29
      2775068.58     10167317.92
#Sta/Elev= 30
  4648.6 1370.35  4741.2 1367.43  4752.8 1366.04  4789.5 1363.34  4815.6 1360.53
  4820.8 1360.72  4850.3 1358.09  4882.7 1356.73  4913.8  1354.5  4929.9 1356.14
  4955.3 1356.67  4963.9 1355.62  4964.5 1355.55  4969.7 1354.28    4976  1351.7
  4986.4 1349.61  5017.4 1350.09  5024.8  1349.5  5025.3    1349  5030.4    1349
  5044.1 1351.83  5078.8 1355.72  5103.5 1356.28  5130.4 1358.85  5167.8  1360.6
  5237.2 1366.68  5271.9 1368.42  5301.6 1371.06  5364.8 1372.75  5388.4 1374.63
#Mann= 6 ,-1 , 0
  4648.6     .05       0  4752.8     .12       0  4963.9     .05       0
  4964.5     .05       0  5078.8     .05       0  5364.8     .12       0
Bank Sta=4964.5,5078.8
XS Rating Curve= 0 ,0
Exp/Cntr=0.3,0.1

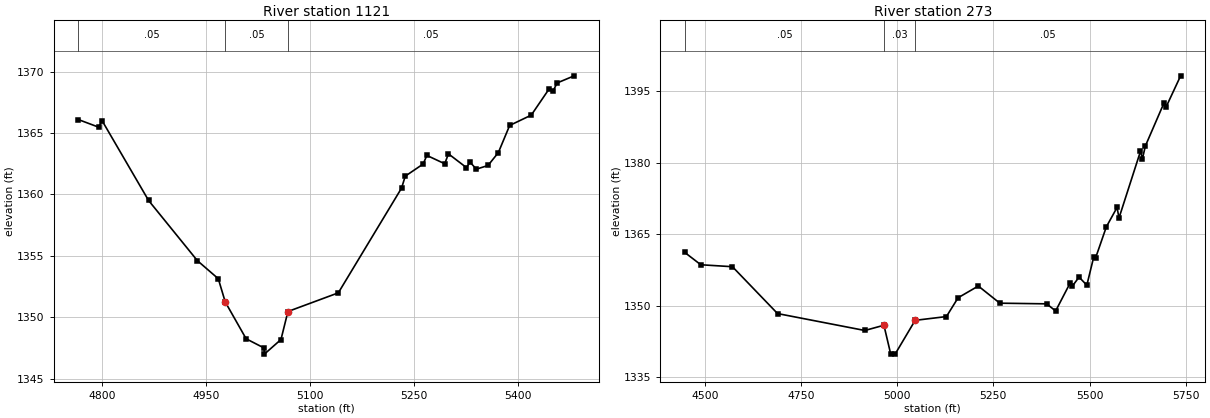
Type RM Length L Ch R = 1 ,1121    ,848,848,848
BEGIN DESCRIPTION:
SOUTH HELMS CREEK 2.0
END DESCRIPTION:
XS GIS Cut Line= 3
      2775393.37     10168003.98      2775362.65     10167633.77
      2775250.34     10167309.97
#Sta/Elev= 30
  4766.2  1366.1  4795.4 1365.48  4800.5    1366  4867.4 1359.51  4937.7 1354.61
  4967.8 1353.14  4977.8 1351.25  5007.9 1348.25  5033.7  1347.5  5034.2    1347
  5058.1 1348.19  5068.1 1350.47  5140.7 1351.99  5231.8 1360.52  5237.1 1361.49
  5262.9 1362.48  5268.2 1363.18    5294  1362.5  5299.3 1363.31  5325.2 1362.19
  5330.5 1362.63  5339.5 1362.06  5356.3 1362.36  5371.2 1363.41  5387.5 1365.62
  5418.6 1366.46  5444.4  1368.6  5449.7 1368.39  5455.9 1369.08  5480.4 1369.66
#Mann= 3 , 0 , 0
  4766.2     .05       0  4977.8     .05       0  5068.1     .05       0
Bank Sta=4977.8,5068.1
XS Rating Curve= 0 ,0
Exp/Cntr=0.3,0.1

Type RM Length L Ch R = 1 ,273     ,0,0,0
BEGIN DESCRIPTION:
SOUTH HELMS CREEK 1.0
END DESCRIPTION:
XS GIS Cut Line= 4
      2775605.71     10167953.11      2776091.82     10167814.95
      2776117.77     10167667.29      2776014.01     10167042.74
#Sta/Elev= 30
  4448.3 1361.15  4489.9 1358.57  4572.1 1358.16  4689.3 1348.33  4916.1 1344.78
  4965.7 1345.88  4983.4 1339.82 4995.25 1339.88  5046.9 1346.91  5128.1  1347.7
  5158.5 1351.65    5211 1354.11  5266.9 1350.51  5388.7 1350.37  5411.9 1348.87
  5449.7 1354.76  5454.7 1354.02  5472.8 1355.98    5493 1354.28  5510.6 1360.11
  5515.6 1359.97  5543.7 1366.53  5571.5 1370.59  5576.6 1368.39  5632.4 1382.38
  5637.5 1380.83  5645.1 1383.49  5693.3 1392.49  5698.4 1391.58  5736.7 1398.21
#Mann= 3 , 0 , 0
  4448.3     .05       0  4965.7     .03       0  5046.9     .05       0
Bank Sta=4965.7,5046.9
XS Rating Curve= 0 ,0
Exp/Cntr=0.3,0.1

Chan Stop Cuts=-1
Use User Specified Reach Order=0
Composite Channel Slope=5