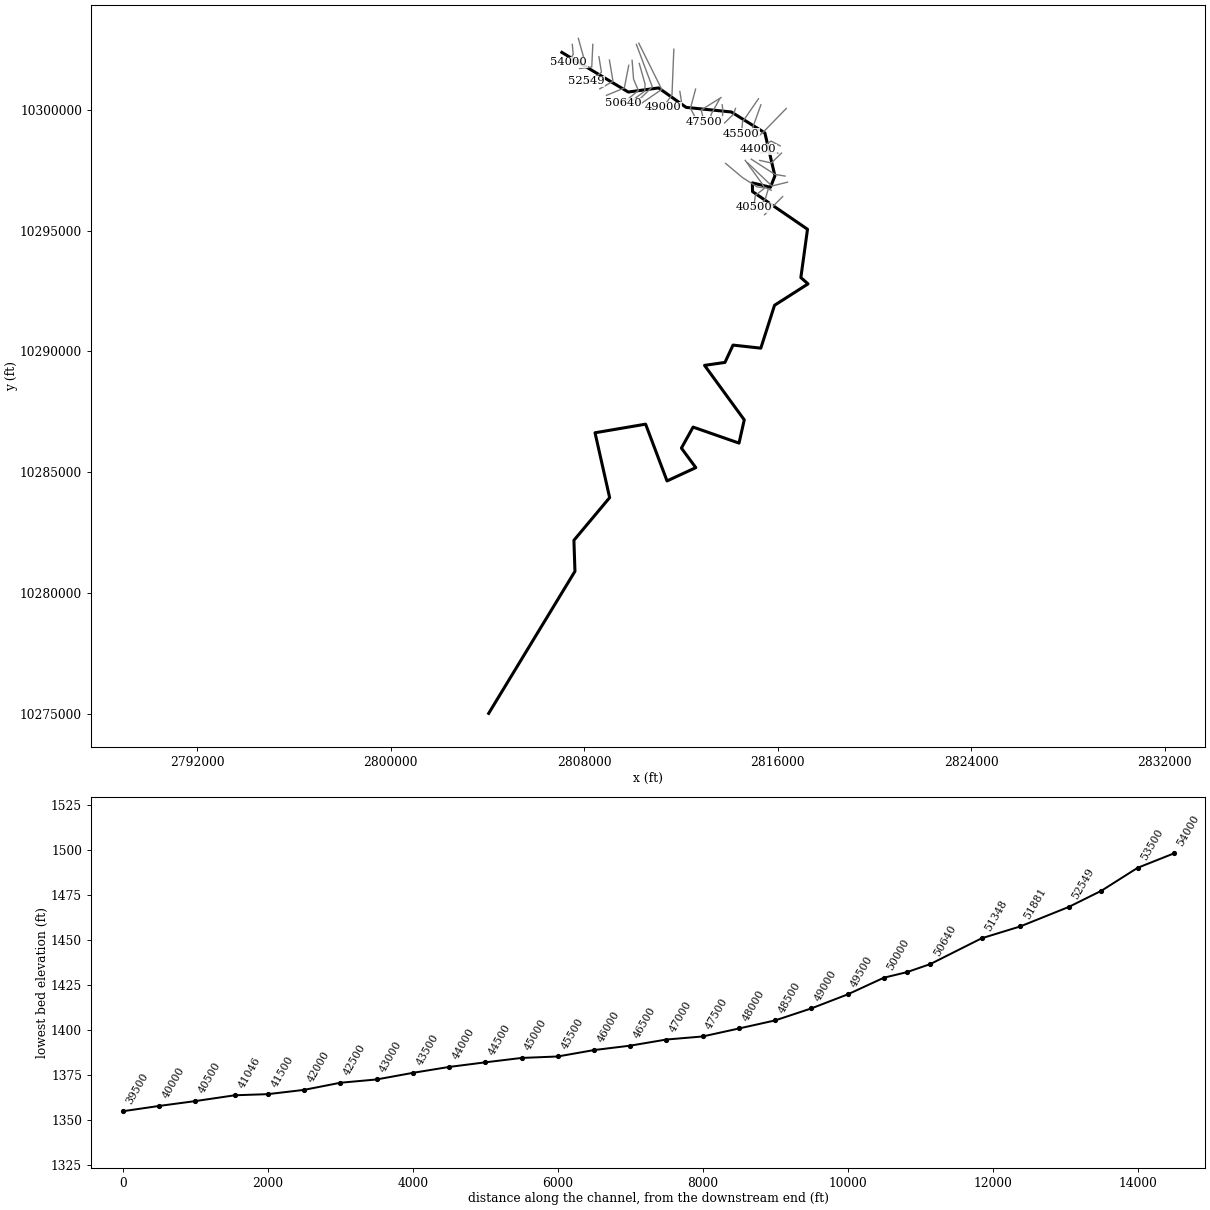
--- BABYHEAD CREEK.prj (project) ---

Proj Title=BABYHEAD CREEK Base Level Engineering
Current Plan=p01
Default Exp/Contr=0.3,0.1
English Units
Geom File=g01
Flow File=f01
Plan File=p01
Y Axis Title=Elevation
X Axis Title(PF)=Main Channel Distance
X Axis Title(XS)=Station
BEGIN DESCRIPTION:
BABYHEAD CREEK
END DESCRIPTION:
DSS Export Rating Curves= 0
DSS Export Rating Curve Sorted= 0
DSS Export Volume Flow Curves= 0
DXF OffsetX= 0
DXF OffsetY= 0
DXF ScaleX= 1
DXF ScaleY= 10

--- BABYHEAD CREEK.p01 (plan) ---

Plan Title=Multiple Run
Short Identifier=Multiple
Geom File=g01
Flow File=f01
Subcritical Flow
K Sum by GR= 0
Std Step Tol= 0.01
Critical Tol= 0.01
Num of Std Step Trials= 20
Max Error Tol= 0.3
Flow Tol Ratio= 0.001
Split Flow NTrial= 30
Split Flow Tol= 0.02
Split Flow Ratio= 0.02
Log Output Level= 0
Friction Slope Method= 1
Unsteady Friction Slope Method= 2
Unsteady Bridges Friction Slope Method= 1
Parabolic Critical Depth
Global Vel Dist=  1 , 1 , 1
Global Log Level= 0
CheckData=True
Encroach Param= -1, 0, 0, 0
BEGIN DESCRIPTION:
Multiple Run
END DESCRIPTION:

--- BABYHEAD CREEK.f01 (steady flow) ---

Flow Title=Multiple
Program Version=4.10
Number of Profiles= 7
Profile Names=10-year,25-year,50-year,1pct_min,100-year,1pct_plu,500-year
River Rch & RM=BABYHEAD CREEK,Reach-1         ,54000
     858    1449    2007    1224    2732    6097    3726
River Rch & RM=BABYHEAD CREEK,Reach-1         ,44500
    1110    1910    2638    1489    3621    8807    4929
River Rch & RM=BABYHEAD CREEK,Reach-1         ,40500
    1230    2134    2895    1835    3983    8642    5419
River Rch & RM=BABYHEAD CREEK,Reach-1         ,37000
    1366    2383    3325    2399    4597    8810    6252
River Rch & RM=BABYHEAD CREEK,Reach-1         ,36000
    1553    2730    3956    2836    5513   10714    7517
River Rch & RM=BABYHEAD CREEK,Reach-1         ,34000
    1731    3072    4378    3407    6118   10986    8338
River Rch & RM=BABYHEAD CREEK,Reach-1         ,30000
    1872    3337    4826    3409    6765   13428    9218
River Rch & RM=BABYHEAD CREEK,Reach-1         ,28500
    2240    4056    5698    3871    8025   16638   10931
River Rch & RM=BABYHEAD CREEK,Reach-1         ,19500
    2677    4910    7104    5623   10096   18129   13773
River Rch & RM=BABYHEAD CREEK,Reach-1         ,13000
    3483    6540   10230    8387   14733   25881   19979
River Rch & RM=BABYHEAD CREEK,Reach-1         ,7417
    3650    6875   10796    9809   15568   24707   21092
River Rch & RM=BABYHEAD CREEK,Reach-1         ,5000
    4142    7853   12444   12882   17987   25115   24299
Boundary for River Rch & Prof#=BABYHEAD CREEK,Reach-1         , 1
Up Type= 0
Dn Type= 3
Dn Slope=0.001
Boundary for River Rch & Prof#=BABYHEAD CREEK,Reach-1         , 2
Up Type= 0
Dn Type= 3
Dn Slope=0.001
Boundary for River Rch & Prof#=BABYHEAD CREEK,Reach-1         , 3
Up Type= 0
Dn Type= 3
Dn Slope=0.001
Boundary for River Rch & Prof#=BABYHEAD CREEK,Reach-1         , 4
Up Type= 0
Dn Type= 3
Dn Slope=0.001
Boundary for River Rch & Prof#=BABYHEAD CREEK,Reach-1         , 5
Up Type= 0
Dn Type= 3
Dn Slope=0.001
Boundary for River Rch & Prof#=BABYHEAD CREEK,Reach-1         , 6
Up Type= 0
Dn Type= 3
Dn Slope=0.001
Boundary for River Rch & Prof#=BABYHEAD CREEK,Reach-1         , 7
Up Type= 0
Dn Type= 3
Dn Slope=0.001
DSS Import GetInterval= 0
DSS Import GetPeak= 0
DSS Import FillOption= 0

--- BABYHEAD CREEK.g01 (geometry) ---

Geom Title=Existing Conditions
Program Version=4.10

River Reach=BABYHEAD CREEK  ,Reach-1
Reach XY= 30
       2807075.5       10302371.      2809822.25       10300731.
      2811076.25       10300901.      2812214.25       10300096.
        2814084.       10299906.        2815470.       10299040.
      2815885.25       10297259.      2815699.25       10296789.
        2814954.       10296971.       2814960.5       10296611.
      2817233.25       10295053.      2816958.25       10293053.
        2817255.       10292792.      2815869.75       10291906.
        2815303.       10290132.      2814153.25       10290259.
      2813819.25       10289542.       2812975.5       10289420.
        2814618.       10287165.        2814401.       10286203.
      2812501.75       10286866.        2812019.       10285996.
       2812613.5       10285188.      2811424.25       10284638.
      2810538.75       10286987.      2808446.75       10286631.
        2809051.       10283947.       2807573.5       10282181.
       2807616.5       10280898.      2804048.75       10275019.

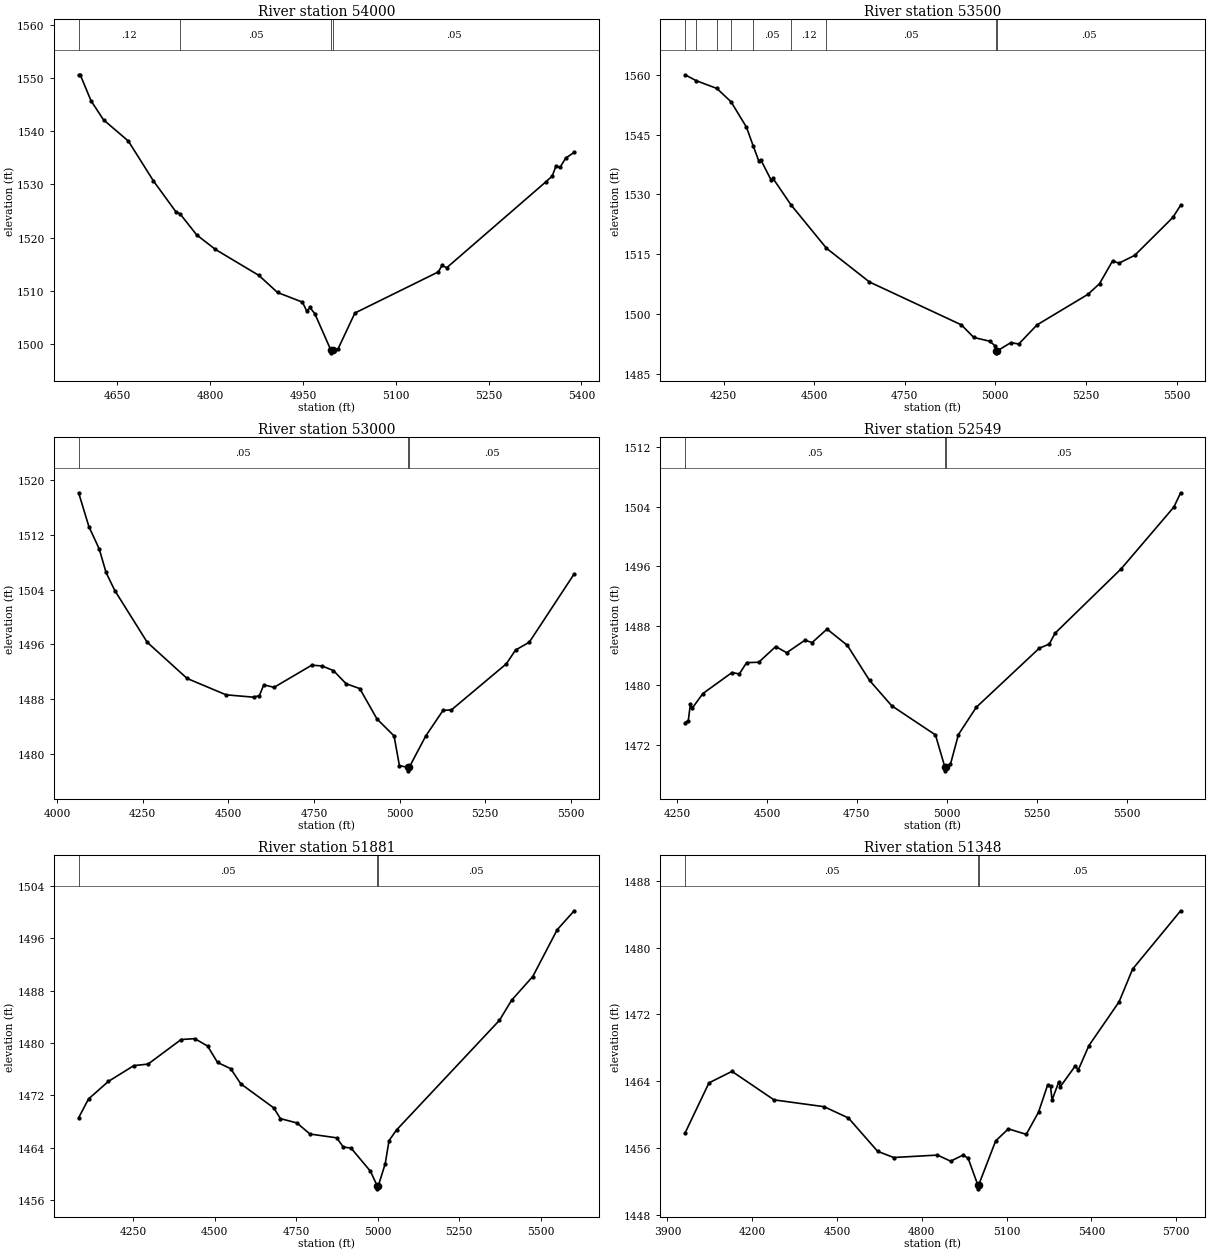
Type RM Length L Ch R = 1 ,54000   ,500,500,500
BEGIN DESCRIPTION:
BABYHEAD CREEK 108.0
END DESCRIPTION:
XS GIS Cut Line= 3
      2807505.68     10302703.16      2807544.61      10302292.4
       2807355.7     10301953.15
#Sta/Elev= 30
  4587.4 1550.58    4590 1550.58  4607.5 1545.68  4627.6 1542.12  4667.8 1538.12
    4708 1530.69  4744.8  1524.8  4751.3 1524.45  4778.3 1520.48  4808.4 1517.77
  4878.7 1512.88  4908.9 1509.67  4949.1 1507.86  4956.2 1506.15  4961.2 1506.85
  4969.1 1505.69  4995.1 1498.83  4995.4 1498.33  4999.1 1498.83  5006.5 1499.03
  5033.9 1505.81  5168.8 1513.54  5174.6 1514.75  5182.3 1514.32  5342.6 1530.47
  5352.9 1531.56  5358.6 1533.36  5365.5 1533.19  5374.6 1534.92  5388.3    1536
#Mann= 4 ,-1 , 0
  4587.4     .12       0  4751.3     .05       0  4995.1     .05       0
  4999.1     .05       0
Bank Sta=4995.1,4999.1
XS Rating Curve= 0 ,0
Exp/Cntr=0.3,0.1

Type RM Length L Ch R = 1 ,53500   ,500,500,500
BEGIN DESCRIPTION:
BABYHEAD CREEK 107.0
END DESCRIPTION:
XS GIS Cut Line= 3
      2807755.69     10302953.09      2807986.02     10302128.66
      2807505.69     10301953.12
#Sta/Elev= 30
    4144 1559.97  4174.5  1558.5  4231.8 1556.54  4270.9 1553.19  4313.3 1546.85
  4332.5 1542.01  4347.4 1538.37  4352.6 1538.72  4381.6 1533.56  4386.8 1533.99
    4436 1527.41  4534.1 1516.52  4652.7 1508.07  4906.5 1497.32  4940.6 1494.17
  4985.2 1493.22    5000 1492.01  5001.6 1490.82  5001.9 1490.32  5005.6 1490.82
  5042.9 1492.88  5064.7 1492.53  5115.1 1497.32  5255.9 1504.99  5287.7 1507.66
  5323.6 1513.34  5341.1 1512.78  5384.6 1514.73  5490.1 1524.25  5511.4  1527.3
#Mann= 9 ,-1 , 0
    4144     .05       0  4174.5     .12       0  4231.8     .05       0
  4270.9     .12       0  4332.5     .05       0    4436     .12       0
  4534.1     .05       0  5001.6     .05       0  5005.6     .05       0
Bank Sta=5001.6,5005.6
XS Rating Curve= 0 ,0
Exp/Cntr=0.3,0.1

Type RM Length L Ch R = 1 ,53000   ,451,451,451
BEGIN DESCRIPTION:
BABYHEAD CREEK 106.0
END DESCRIPTION:
XS GIS Cut Line= 3
      2808355.68     10302703.12      2808311.48     10301767.07
      2807805.71     10301703.12
#Sta/Elev= 30
  4062.9 1518.12  4092.9 1513.18    4123 1509.93    4143 1506.49  4168.5 1503.86
  4263.1 1496.31  4379.6 1491.03  4493.4 1488.64  4573.5  1488.3  4590.7 1488.53
  4603.5  1490.1  4633.5 1489.73  4743.7 1492.97  4773.7 1492.85  4806.9 1492.18
  4843.8 1490.26  4883.8 1489.55  4933.9 1485.13  4983.9 1482.64  4999.5 1478.32
    5024 1478.05  5024.3 1477.55    5028 1478.05  5076.4 1482.63  5126.8 1486.36
  5151.6 1486.45  5311.9 1493.17  5338.5 1495.17  5378.8 1496.32  5509.8 1506.28
#Mann= 3 ,-1 , 0
  4062.9     .05       0    5024     .05       0    5028     .05       0
Bank Sta=5024,5028
XS Rating Curve= 0 ,0
Exp/Cntr=0.3,0.1

Type RM Length L Ch R = 1 ,52549   ,668,668,668
BEGIN DESCRIPTION:
Mapping XS e027b2ff
END DESCRIPTION:
XS GIS Cut Line= 4
       2808608.2     10302191.87      2808712.36     10301549.52
       2808564.8     10301427.99      2808096.52     10301167.84
#Sta/Elev= 30
  4272.6 1475.02  4281.5 1475.29  4287.3 1477.49  4292.4 1476.95    4322 1478.91
    4403 1481.73  4423.3 1481.54  4443.6 1483.06  4477.3 1483.11  4524.6 1485.22
    4555 1484.39  4605.6 1486.06  4625.9 1485.76  4667.2 1487.56  4723.8 1485.37
  4785.4 1480.67    4847 1477.27  4968.6 1473.36  4994.8 1469.04    4995 1468.54
  4998.8 1469.04  5010.2  1469.4  5032.4  1473.4  5081.9 1477.06  5257.4    1485
  5285.1 1485.55  5300.9    1487  5485.1 1495.66  5631.5 1503.94  5650.2 1505.85
#Mann= 3 ,-1 , 0
  4272.6     .05       0  4994.8     .05       0  4998.8     .05       0
Bank Sta=4994.8,4998.8
XS Rating Curve= 0 ,0
Exp/Cntr=0.3,0.1

Type RM Length L Ch R = 1 ,51881   ,533,533,533
BEGIN DESCRIPTION:
Mapping XS 8dc7fc27
END DESCRIPTION:
XS GIS Cut Line= 3
      2809042.23     10302052.95       2809189.8     10301176.26
      2808642.91     10300863.75
#Sta/Elev= 30
  4083.3 1468.58  4113.6 1471.46  4174.4 1474.14  4252.6 1476.56  4296.1 1476.79
  4397.5 1480.55  4439.3 1480.68  4478.6 1479.55    4509 1477.05  4549.6 1476.08
    4580 1473.79  4681.5 1470.09  4701.7 1468.46  4752.4 1467.79  4792.4  1466.1
  4874.1 1465.52  4894.4 1464.13  4918.6 1463.93  4977.6 1460.42  4998.1 1458.22
  4998.3 1457.72  5002.1 1458.22  5023.1 1461.57  5034.7 1465.09  5057.7 1466.72
  5373.1 1483.48  5410.5 1486.56  5475.3 1490.18  5550.1 1497.33  5602.2 1500.23
#Mann= 3 ,-1 , 0
  4083.3     .05       0  4998.1     .05       0  5002.1     .05       0
Bank Sta=4998.1,5002.1
XS Rating Curve= 0 ,0
Exp/Cntr=0.3,0.1

Type RM Length L Ch R = 1 ,51348   ,708,708,708
BEGIN DESCRIPTION:
Mapping XS 219fdd06
END DESCRIPTION:
XS GIS Cut Line= 3
      2809840.83     10301835.94      2809658.55     10300898.48
      2808920.67     10300594.65
#Sta/Elev= 30
  3962.5 1457.81  4046.9  1463.8  4128.4 1465.18  4276.9 1461.77  4454.4 1460.95
  4540.3  1459.6  4643.6 1455.61  4700.4 1454.87  4855.3 1455.16  4901.9 1454.43
  4946.2 1455.17  4963.9 1454.77  4997.5 1451.62  4997.7 1451.12  5001.5 1451.62
  5061.2 1456.86  5106.1  1458.3  5169.3 1457.64  5212.7 1460.29    5245 1463.55
  5255.2 1463.37  5260.6 1461.76  5284.5 1463.92  5289.9 1463.35  5343.2 1465.85
  5353.2 1465.34  5391.1 1468.27  5497.7  1473.5  5545.6 1477.42  5715.5  1484.4
#Mann= 3 ,-1 , 0
  3962.5     .05       0  4997.5     .03       0  5001.5     .05       0
Bank Sta=4997.5,5001.5
XS Rating Curve= 0 ,0
Exp/Cntr=0.3,0.1

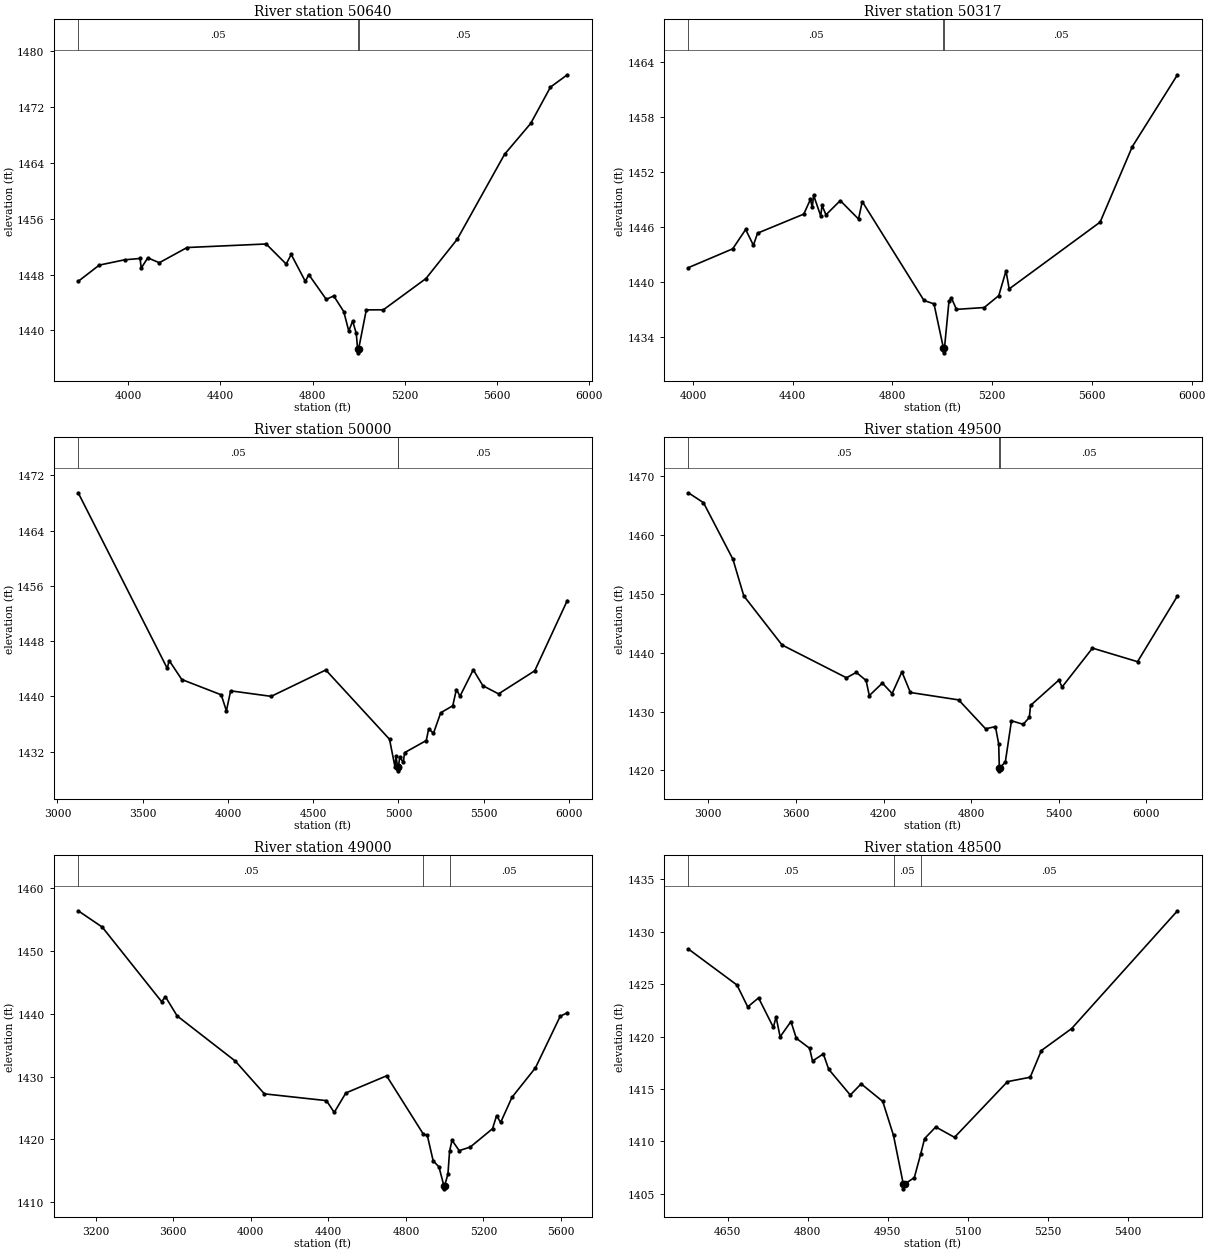
Type RM Length L Ch R = 1 ,50640   ,323,323,323
BEGIN DESCRIPTION:
Mapping XS f5f02ae0
END DESCRIPTION:
XS GIS Cut Line= 4
      2809979.72     10302044.34      2810040.49     10301263.06
      2810240.14     10300794.31      2809599.26     10300266.02
#Sta/Elev= 30
  3782.4 1447.03  3873.9 1449.36  3984.2 1450.12  4051.1 1450.31  4056.1 1448.93
  4084.5  1450.4  4134.7  1449.7  4255.1 1451.88  4598.6 1452.39  4685.6 1449.51
  4707.3 1450.89  4768.9 1447.01  4783.4 1448.01  4859.5 1444.45  4892.1 1444.94
  4935.5 1442.69  4957.3 1439.91  4974.2 1441.34  4989.9 1439.56  4995.8 1437.28
  4996.1 1436.78  4999.8 1437.28  5033.4 1442.94  5107.4 1442.95  5292.4 1447.43
    5428 1453.06  5633.8 1465.25  5747.2 1469.67    5833 1474.88  5906.1 1476.65
#Mann= 3 ,-1 , 0
  3782.4     .05       0  4995.8     .05       0  4999.8     .05       0
Bank Sta=4995.8,4999.8
XS Rating Curve= 0 ,0
Exp/Cntr=0.3,0.1

Type RM Length L Ch R = 1 ,50317   ,317,317,317
BEGIN DESCRIPTION:
Mapping XS 32905498
END DESCRIPTION:
XS GIS Cut Line= 4
      2810274.86     10301914.11      2810517.92     10301054.73
      2810500.56     10300768.27      2809875.58     10300299.53
#Sta/Elev= 30
  3981.9 1441.57  4159.6 1443.62  4211.6 1445.73  4242.7 1444.01  4259.4 1445.33
  4444.8 1447.41  4471.4 1449.02  4478.8 1448.13    4484 1449.47  4512.7  1447.2
  4517.9 1448.36  4533.7 1447.33    4591 1448.88  4664.2 1446.87  4679.2 1448.77
  4926.7 1437.99  4966.8 1437.62  5004.8 1432.78  5005.1 1432.28  5008.8 1432.78
  5026.9 1437.91  5036.9 1438.25  5056.9 1437.02  5168.3 1437.22  5226.6 1438.52
  5255.6 1441.22  5268.3 1439.25  5632.9 1446.53    5762 1454.76  5943.2  1462.6
#Mann= 3 ,-1 , 0
  3981.9     .05       0  5004.8     .05       0  5008.8     .05       0
Bank Sta=5004.8,5008.8
XS Rating Curve= 0 ,0
Exp/Cntr=0.3,0.1

Type RM Length L Ch R = 1 ,50000   ,500,500,500
BEGIN DESCRIPTION:
BABYHEAD CREEK 100.0
END DESCRIPTION:
XS GIS Cut Line= 3
      2810155.68     10302703.13      2810815.46     10300944.42
      2810105.69     10300253.11
#Sta/Elev= 30
  3121.6 1469.48    3644 1444.05  3655.6 1445.17  3729.4 1442.43  3960.8 1440.21
    3991 1437.89  4015.9 1440.79  4253.8 1439.99  4574.2 1443.81    4948 1433.77
    4980 1429.77  4985.9 1431.31    4996  1429.7  4996.3  1429.2    5000  1429.7
  5007.9 1431.21    5029 1430.42  5036.1 1431.83  5163.5 1433.59  5177.6 1435.27
  5205.9 1434.65  5248.3 1437.61  5319.1 1438.63  5340.2 1440.98  5361.5 1440.02
  5439.2 1443.84  5495.8 1441.53  5587.6 1440.35  5799.8 1443.69  5990.8 1453.87
#Mann= 3 ,-1 , 0
  3121.6     .05       0    4996     .05       0    5000     .05       0
Bank Sta=4996,5000
XS Rating Curve= 0 ,0
Exp/Cntr=0.3,0.1

Type RM Length L Ch R = 1 ,49500   ,500,500,500
BEGIN DESCRIPTION:
BABYHEAD CREEK 99.0
END DESCRIPTION:
XS GIS Cut Line= 3
      2810255.69      10302753.1      2811206.31      10300839.4
      2810205.65     10300153.09
#Sta/Elev= 30
  2863.2 1467.22  2966.8 1465.53  3168.4 1455.91  3242.8 1449.68  3504.5 1441.33
  3946.3 1435.74  4013.3 1436.66  4080.3 1435.29  4102.6 1432.71  4191.9 1434.84
  4258.9 1433.06  4325.9 1436.75  4383.9 1433.24  4714.4 1431.98  4899.2 1427.06
  4966.4 1427.44  4988.8 1424.48  4993.1 1420.41  4993.4 1419.91  4997.1 1420.41
  5034.4 1421.45  5076.3 1428.43  5156.9 1427.82  5198.8 1429.01  5206.9 1431.04
  5400.9 1435.35  5422.9 1434.17  5631.3 1440.79  5939.9 1438.48  6213.4 1449.66
#Mann= 3 ,-1 , 0
  2863.2     .05       0  4993.1     .05       0  4997.1     .05       0
Bank Sta=4993.1,4997.1
XS Rating Curve= 0 ,0
Exp/Cntr=0.3,0.1

Type RM Length L Ch R = 1 ,49000   ,500,500,500
BEGIN DESCRIPTION:
BABYHEAD CREEK 98.0
END DESCRIPTION:
XS GIS Cut Line= 3
      2811705.68     10302503.08      2811629.21     10300613.62
      2811255.67     10300103.09
#Sta/Elev= 30
    3109  1456.4  3233.3  1453.8  3539.3 1441.94  3559.3 1442.71  3619.4 1439.67
  3919.6 1432.48  4069.8 1427.26    4390 1426.18    4430  1424.3  4490.1  1427.4
  4700.3 1430.13  4890.4 1420.82  4910.4 1420.64  4940.5 1416.61  4970.5 1415.63
  4995.8 1412.64    4996 1412.14  4999.8 1412.64  5016.8  1414.5  5025.3 1418.14
  5037.8 1419.87    5075 1418.22  5131.9 1418.79  5246.9 1421.71  5267.8 1423.79
  5288.6  1422.7  5347.3 1426.71  5468.5 1431.41  5595.9  1439.6  5632.6 1440.17
#Mann= 3 ,-1 , 0
    3109     .05       0  4890.4     .05       0  5025.3     .05       0
Bank Sta=4995.8,4999.8
XS Rating Curve= 0 ,0
Exp/Cntr=0.3,0.1

Type RM Length L Ch R = 1 ,48500   ,500,500,500
BEGIN DESCRIPTION:
BABYHEAD CREEK 97.0
END DESCRIPTION:
XS GIS Cut Line= 3
      2811955.69      10300753.1      2812021.11     10300334.58
      2811655.65     10300003.09
#Sta/Elev= 30
  4576.4 1428.36  4667.5 1424.92  4687.7 1422.83    4708 1423.69  4735.8 1420.87
  4740.8 1421.88  4748.4 1419.97  4768.7 1421.43  4778.8 1419.83  4803.6 1418.88
  4809.2 1417.66  4829.4 1418.34  4839.5 1416.87    4880 1414.41  4900.3 1415.48
  4940.8  1413.8    4961 1410.55  4979.2 1405.95  4979.5 1405.45  4983.2 1405.95
    5000 1406.52  5011.8 1408.74  5019.3 1410.25  5040.2 1411.36  5075.4 1410.37
  5174.7 1415.69  5217.3 1416.11  5238.2 1418.66    5295 1420.76  5493.4 1432.01
#Mann= 3 ,-1 , 0
  4576.4     .05       0    4961     .05       0  5011.8     .05       0
Bank Sta=4979.2,4983.2
XS Rating Curve= 0 ,0
Exp/Cntr=0.3,0.1

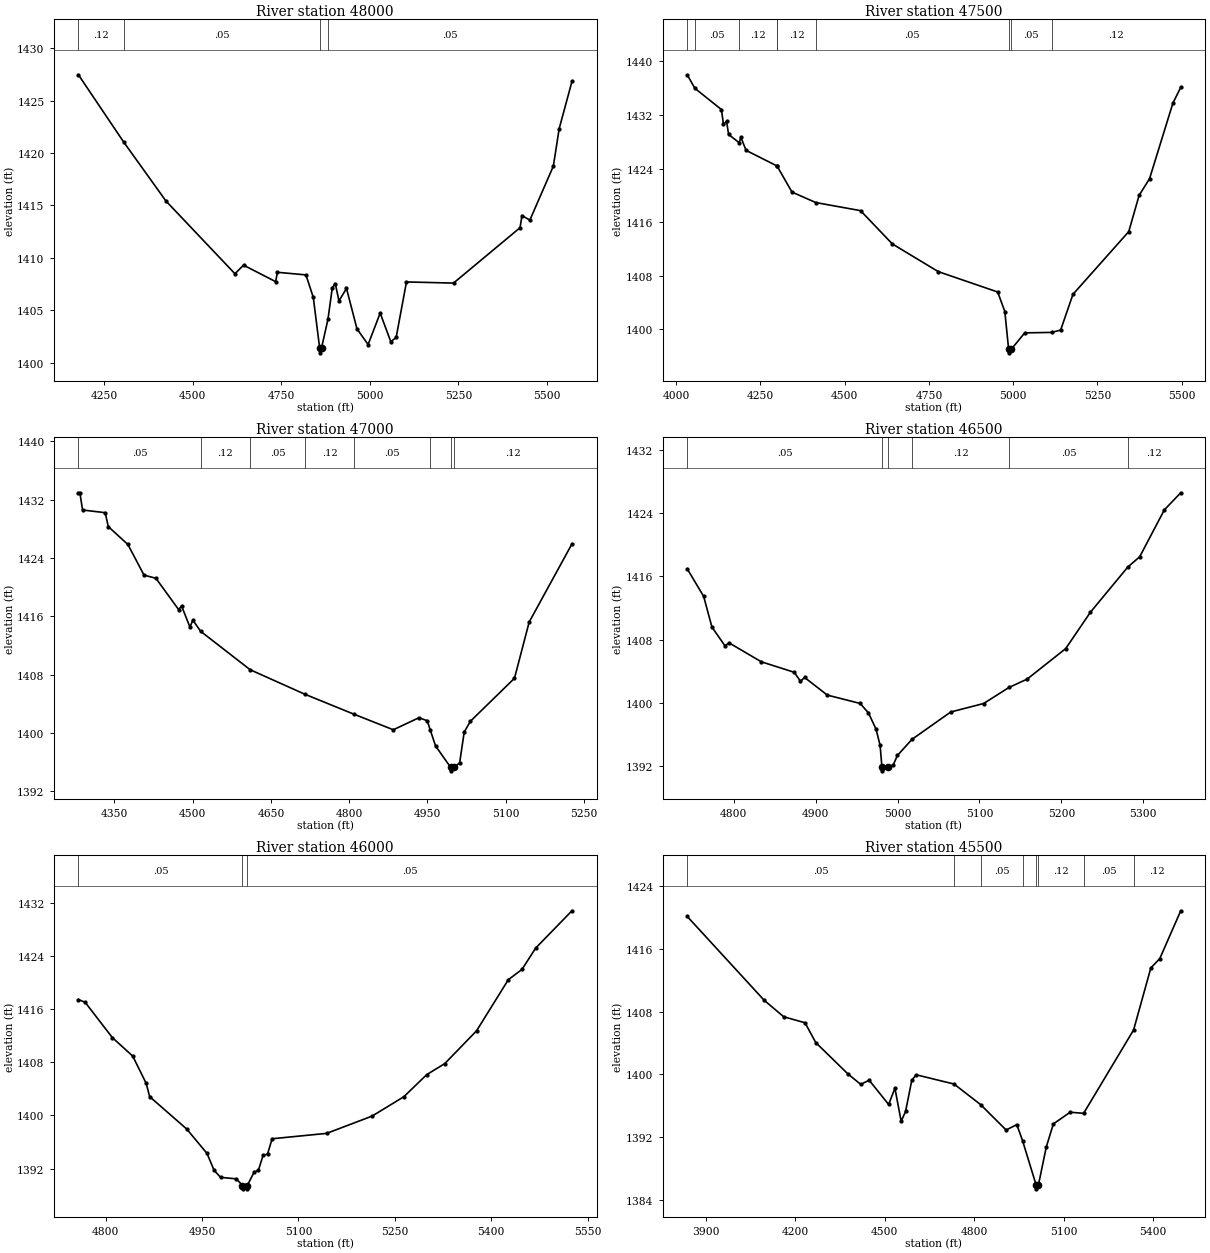
Type RM Length L Ch R = 1 ,48000   ,500,500,500
BEGIN DESCRIPTION:
BABYHEAD CREEK 96.0
END DESCRIPTION:
XS GIS Cut Line= 3
      2812605.68     10300853.09      2812392.45     10300059.23
      2812655.69      10299553.1
#Sta/Elev= 30
    4178 1427.46  4305.5 1421.06  4424.9 1415.43  4619.7 1408.49  4643.9 1409.31
  4734.4 1407.74  4739.6 1408.63    4820 1408.38  4840.7 1406.24  4858.5 1401.45
    4859 1400.95  4864.2 1401.45  4882.1 1404.15  4894.4 1407.17  4902.8 1407.55
  4913.1  1405.9  4934.4 1407.09    4964 1403.23  4995.4 1401.74  5029.4 1404.74
  5059.4 1402.01  5074.5 1402.42  5103.6 1407.71  5236.3  1407.6    5424 1412.88
  5429.6 1414.04  5451.7  1413.6    5518 1418.75  5534.5 1422.33  5570.5 1426.82
#Mann= 4 ,-1 , 0
    4178     .12       0  4305.5     .05       0  4858.5     .05       0
  4882.1     .05       0
Bank Sta=4858.5,4864.2
XS Rating Curve= 0 ,0
Exp/Cntr=0.3,0.1

Type RM Length L Ch R = 1 ,47500   ,500,500,500
BEGIN DESCRIPTION:
BABYHEAD CREEK 95.0
END DESCRIPTION:
XS GIS Cut Line= 3
      2813655.66      10300503.1      2812837.51     10299986.49
      2812955.68     10299503.13
#Sta/Elev= 30
  4032.4 1438.01  4055.4 1435.98  4134.1 1432.82  4140.1 1430.62  4149.4 1431.04
  4155.3 1429.11  4186.7 1427.87  4191.8 1428.69  4207.1 1426.73  4298.3 1424.42
  4299.9 1424.33  4343.6  1420.5  4414.2 1418.94  4547.1 1417.73  4641.3 1412.77
  4777.8 1408.63  4954.2 1405.59  4975.4 1402.67  4986.7 1397.01  4987.2 1396.51
    4994 1397.01  5034.4 1399.49  5114.2 1399.56  5141.1 1399.91  5177.6 1405.24
  5343.2  1414.6  5374.1 1420.02    5405  1422.5  5474.2 1433.76  5497.6 1436.13
#Mann= 9 ,-1 , 0
  4032.4     .12       0  4055.4     .05       0  4186.7     .12       0
  4298.3     .05       0  4299.9     .12       0  4414.2     .05       0
  4986.7     .05       0    4994     .05       0  5114.2     .12       0
Bank Sta=4986.7,4994
XS Rating Curve= 0 ,0
Exp/Cntr=0.3,0.1

Type RM Length L Ch R = 1 ,47000   ,500,500,500
BEGIN DESCRIPTION:
BABYHEAD CREEK 94.0
END DESCRIPTION:
XS GIS Cut Line= 3
      2813605.67     10300453.08      2813256.03     10299824.59
      2813205.69     10299603.14
#Sta/Elev= 30
  4280.8 1432.93  4283.6 1432.93  4288.8 1430.57  4332.2  1430.2    4338  1428.3
  4375.7 1425.84  4406.6 1421.64  4429.4 1421.21  4472.9 1416.92  4478.6 1417.42
  4494.6 1414.52  4500.3 1415.47    4515 1413.95  4610.1 1408.67  4715.4  1405.3
  4808.9 1402.58  4884.6 1400.44  4933.7 1402.09  4949.7 1401.68  4955.5 1400.38
  4965.7 1398.21  4994.3 1395.31  4994.8 1394.81  5001.7 1395.31  5011.8 1395.92
  5020.5 1400.12  5032.3  1401.6  5116.9  1407.5  5145.1 1415.21  5227.1 1425.92
#Mann= 8 ,-1 , 0
  4280.8     .05       0    4515     .12       0  4610.1     .05       0
  4715.4     .12       0  4808.9     .05       0  4955.5     .12       0
  4994.3     .07       0  5001.7     .12       0
Bank Sta=4994.3,5001.7
XS Rating Curve= 0 ,0
Exp/Cntr=0.3,0.1

Type RM Length L Ch R = 1 ,46500   ,500,500,500
BEGIN DESCRIPTION:
BABYHEAD CREEK 93.0
END DESCRIPTION:
XS GIS Cut Line= 3
      2813705.68     10300203.11      2813733.04     10299947.77
      2813705.69     10299603.15
#Sta/Elev= 30
  4743.2 1416.95  4763.3 1413.46  4773.4 1409.58  4789.3 1407.21  4794.3 1407.58
  4833.7 1405.19  4873.9 1403.86  4881.5 1402.72  4886.5 1403.21  4914.2 1400.98
  4954.4 1399.92  4964.5 1398.72  4973.7 1396.68  4978.7 1394.62  4980.9  1391.9
  4981.4  1391.4  4988.3  1391.9  4994.6 1392.11  4999.8 1393.34  5017.6 1395.38
  5064.9 1398.84    5105 1399.91    5136 1401.94  5158.2    1403  5205.3 1406.86
  5235.4 1411.45  5281.1 1417.17  5295.6 1418.47  5325.7  1424.4  5345.7 1426.56
#Mann= 6 ,-1 , 0
  4743.2     .05       0  4980.9     .05       0  4988.3     .05       0
  5017.6     .12       0    5136     .05       0  5281.1     .12       0
Bank Sta=4980.9,4988.3
XS Rating Curve= 0 ,0
Exp/Cntr=0.3,0.1

Type RM Length L Ch R = 1 ,46000   ,500,500,500
BEGIN DESCRIPTION:
BABYHEAD CREEK 92.0
END DESCRIPTION:
XS GIS Cut Line= 3
      2814255.69     10300053.13       2814179.3     10299823.08
      2813805.69     10299453.11
#Sta/Elev= 30
  4757.6 1417.44  4768.2 1417.01  4810.4 1411.71  4842.1 1408.93    4863 1404.84
  4868.5 1402.82  4926.2 1397.94  4957.8 1394.27  4968.8 1391.73  4978.9 1390.67
  5003.5 1390.44    5013 1389.44  5013.5 1388.94    5020 1388.94  5020.5 1389.44
  5030.8  1391.4  5037.9 1391.77    5045 1393.97    5052 1394.18  5059.1 1396.48
    5144 1397.29  5214.7 1399.89  5264.2 1402.81  5299.6 1406.12  5327.8 1407.79
  5377.3 1412.73  5426.8 1420.43    5448 1421.97  5469.3 1425.18  5525.8  1430.8
#Mann= 3 ,-1 , 0
  4757.6     .05       0    5013     .05       0  5020.5     .05       0
Bank Sta=5013,5020.5
XS Rating Curve= 0 ,0
Exp/Cntr=0.3,0.1

Type RM Length L Ch R = 1 ,45500   ,500,500,500
BEGIN DESCRIPTION:
BABYHEAD CREEK 91.0
END DESCRIPTION:
XS GIS Cut Line= 3
      2815205.67     10300453.09      2814545.97     10299494.94
      2814505.68     10299003.08
#Sta/Elev= 30
  3836.7 1420.16    4095 1409.46  4160.7 1407.35  4232.3 1406.58  4268.2 1404.06
  4375.7 1400.07  4419.4 1398.71  4447.4 1399.25    4513 1396.15    4534 1398.23
    4555    1394  4569.8 1395.26  4590.8 1399.27  4605.7 1399.94  4732.5 1398.76
  4821.8 1396.13  4907.3 1392.89  4943.2 1393.58  4962.4 1391.54    5008 1385.88
  5008.5 1385.38  5015.8 1385.88    5042  1390.7  5065.9 1393.67  5122.2 1395.16
  5167.5 1395.02  5335.3 1405.67  5393.1 1413.58  5423.2 1414.78  5493.5 1420.88
#Mann= 8 ,-1 , 0
  3836.7     .05       0  4732.5     .12       0  4821.8     .05       0
  4962.4     .12       0    5008     .07       0  5015.8     .12       0
  5167.5     .05       0  5335.3     .12       0
Bank Sta=5008,5015.8
XS Rating Curve= 0 ,0
Exp/Cntr=0.3,0.1

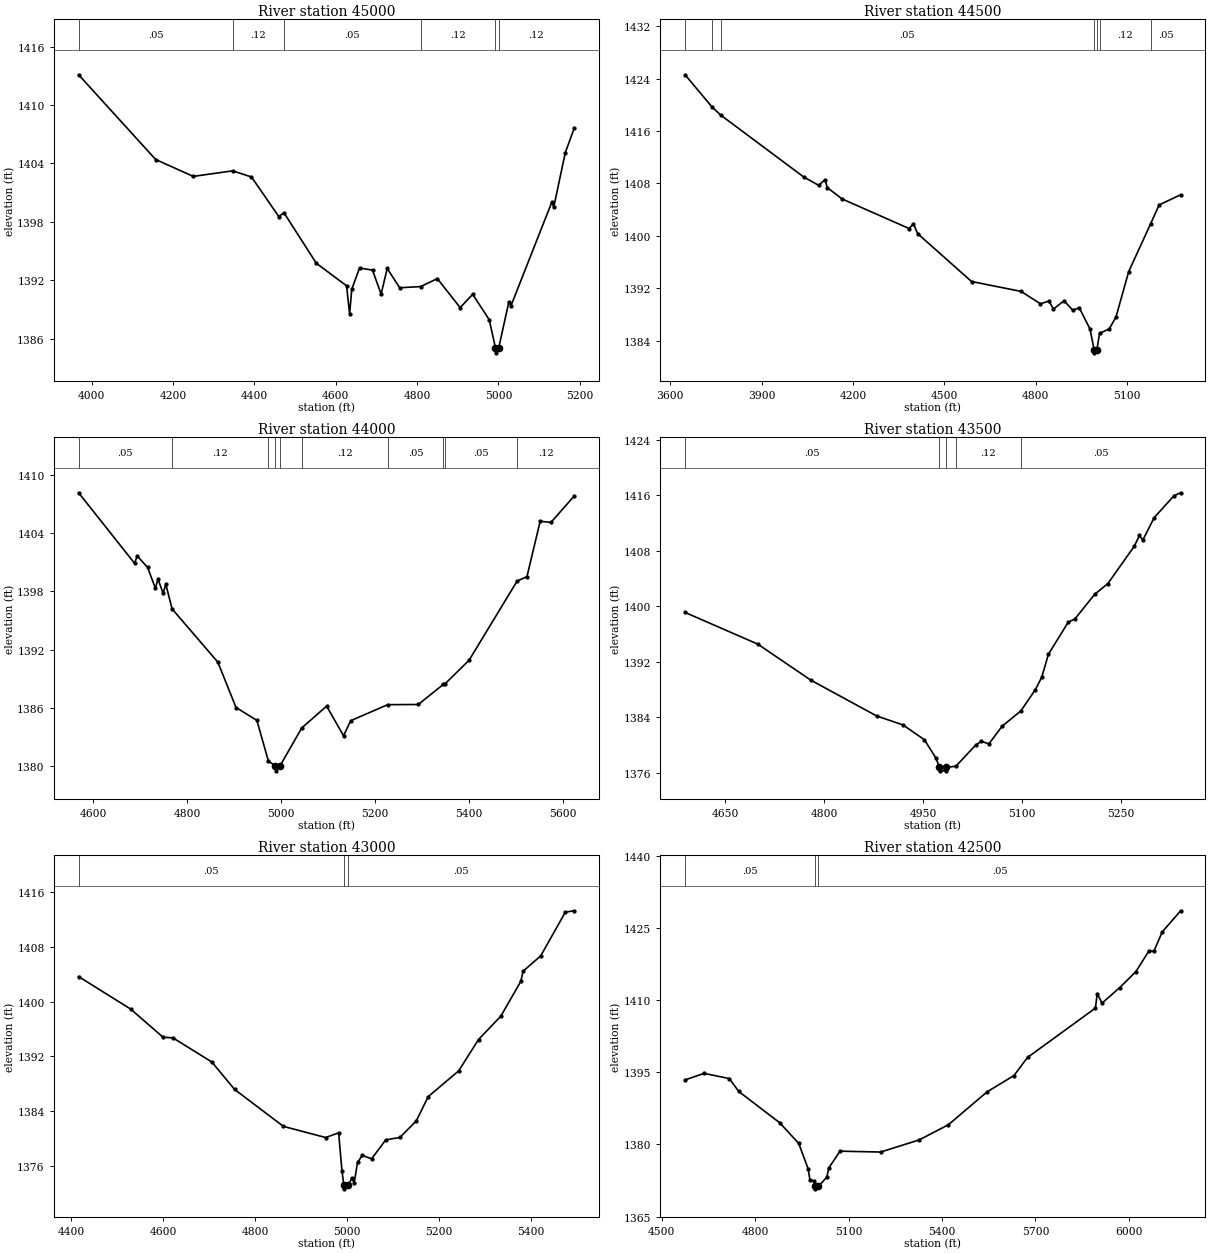
Type RM Length L Ch R = 1 ,45000   ,500,500,500
BEGIN DESCRIPTION:
BABYHEAD CREEK 90.0
END DESCRIPTION:
XS GIS Cut Line= 3
      2815305.69     10300203.12      2814958.18      10299231.6
       2814905.7     10299053.16
#Sta/Elev= 30
  3968.2  1413.1  4157.6  1404.4    4250 1402.67  4346.6 1403.24    4393 1402.61
  4460.1 1398.55  4472.7 1398.94  4552.4 1393.75  4626.7 1391.44  4634.1 1388.55
  4639.4 1391.08  4658.5 1393.27  4690.4 1393.05  4711.6 1390.59  4726.5 1393.22
  4757.2 1391.24  4808.7 1391.36  4849.7 1392.18  4905.8  1389.2  4936.6 1390.57
  4977.2 1387.96  4992.6 1385.06  4993.1 1384.56  5000.5 1385.06  5025.5 1389.79
  5030.7 1389.39  5130.8    1400    5136 1399.55  5164.2 1405.11    5186  1407.6
#Mann= 6 ,-1 , 0
  3968.2     .05       0  4346.6     .12       0  4472.7     .05       0
  4808.7     .12       0  4992.6     .07       0  5000.5     .12       0
Bank Sta=4992.6,5000.5
XS Rating Curve= 0 ,0
Exp/Cntr=0.3,0.1

Type RM Length L Ch R = 1 ,44500   ,500,500,500
BEGIN DESCRIPTION:
BABYHEAD CREEK 89.0
END DESCRIPTION:
XS GIS Cut Line= 3
      2816355.71     10300053.14      2815415.01     10299083.45
      2815205.68     10298903.11
#Sta/Elev= 30
    3649 1424.57  3738.1 1419.62  3765.3 1418.44  4038.1 1408.98  4087.5  1407.7
  4108.8 1408.56  4115.8 1407.35  4165.2  1405.6  4384.6  1401.1  4398.7 1401.81
  4412.9 1400.31  4589.6 1393.01  4752.2  1391.5  4815.9 1389.61  4844.2 1390.02
  4858.4  1388.8  4893.6 1390.07  4921.9 1388.64  4943.3    1389  4978.5 1385.77
  4992.2 1382.62  4992.7 1382.12  5001.3 1382.62  5010.1 1385.09  5042.1 1385.79
    5064 1387.59  5105.7 1394.52  5178.1 1401.86  5205.5  1404.7  5276.3 1406.25
#Mann= 7 ,-1 , 0
    3649     .05       0  3738.1     .12       0  3765.3     .05       0
  4992.2     .03       0  5001.3     .05       0  5010.1     .12       0
  5178.1     .05       0
Bank Sta=4992.2,5001.3
XS Rating Curve= 0 ,0
Exp/Cntr=0.3,0.1

Type RM Length L Ch R = 1 ,44000   ,500,500,500
BEGIN DESCRIPTION:
BABYHEAD CREEK 88.0
END DESCRIPTION:
XS GIS Cut Line= 3
      2816105.65     10298503.13      2815723.13     10298700.84
      2815205.71     10298353.13
#Sta/Elev= 30
  4569.4 1408.13  4688.4 1400.88    4694 1401.64  4716.1 1400.46  4732.6 1398.32
  4738.3 1399.25  4749.2 1397.78  4754.8 1398.74  4768.1  1396.2  4865.5 1390.72
  4904.2 1386.06  4948.5 1384.74    4973 1380.56    4988 1380.05  4988.5 1379.55
  4997.6 1380.05    5044 1383.96  5096.9  1386.2  5132.9 1383.15  5147.9  1384.7
  5226.7 1386.35  5291.9 1386.37  5345.4 1388.45  5348.1 1388.46  5399.9 1390.92
  5502.2 1399.07  5522.9  1399.5  5551.1 1405.21  5573.9 1405.08  5623.4 1407.79
#Mann= 10 ,-1 , 0
  4569.4     .05       0  4768.1     .12       0    4973     .05       0
    4988     .05       0  4997.6     .05       0    5044     .12       0
  5226.7     .05       0  5345.4     .12       0  5348.1     .05       0
  5502.2     .12       0
Bank Sta=4988,4997.6
XS Rating Curve= 0 ,0
Exp/Cntr=0.3,0.1

Type RM Length L Ch R = 1 ,43500   ,500,500,500
BEGIN DESCRIPTION:
BABYHEAD CREEK 87.0
END DESCRIPTION:
XS GIS Cut Line= 3
      2816005.68     10298203.11      2815595.57     10298231.62
      2815255.67     10298203.11
#Sta/Elev= 30
  4588.9 1399.11  4699.2 1394.54  4779.4 1389.36  4879.6 1384.18  4919.7 1382.88
  4952.1 1380.75  4969.8 1378.08    4975 1376.76  4975.5 1376.26  4984.2 1376.26
  4984.7 1376.76  4999.9 1376.92    5030 1379.98  5038.5 1380.51  5050.1 1380.16
  5070.1 1382.69  5098.7 1384.92  5120.3 1387.93  5130.3 1389.77  5140.4 1393.08
  5170.5 1397.71  5180.5 1398.16  5210.6 1401.72  5230.7 1403.28  5270.8 1408.67
  5278.6 1410.22  5283.6 1409.53  5300.9 1412.78    5331 1415.94  5341.1 1416.37
#Mann= 5 ,-1 , 0
  4588.9     .05       0    4975     .07       0  4984.7     .05       0
  4999.9     .12       0  5098.7     .05       0
Bank Sta=4975,4984.7
XS Rating Curve= 0 ,0
Exp/Cntr=0.3,0.1

Type RM Length L Ch R = 1 ,43000   ,500,500,500
BEGIN DESCRIPTION:
BABYHEAD CREEK 86.0
END DESCRIPTION:
XS GIS Cut Line= 3
      2816155.68     10298203.11       2815738.1     10297795.12
      2815255.64     10297903.12
#Sta/Elev= 30
  4416.2 1403.65  4529.3  1398.9    4600 1394.77  4621.3 1394.69  4706.2 1391.14
  4755.6 1387.13  4861.8 1381.73  4953.6  1380.1  4981.9 1380.78  4989.1 1375.26
  4993.3 1373.09  4993.8 1372.59    5003 1373.09  5010.6 1374.16  5015.8 1373.47
    5023 1376.47  5033.2 1377.47  5053.7 1376.99  5084.5 1379.76  5115.2 1380.11
    5151 1382.54  5176.7 1386.08  5242.9 1389.84  5286.3 1394.44  5334.8 1397.86
  5378.2 1402.94  5383.3 1404.44  5421.6 1406.68  5475.2 1413.08  5494.4 1413.28
#Mann= 3 ,-1 , 0
  4416.2     .05       0  4993.3     .05       0    5003     .05       0
Bank Sta=4993.3,5003
XS Rating Curve= 0 ,0
Exp/Cntr=0.3,0.1

Type RM Length L Ch R = 1 ,42500   ,500,500,500
BEGIN DESCRIPTION:
BABYHEAD CREEK 85.0
END DESCRIPTION:
XS GIS Cut Line= 3
      2816305.67     10297253.11      2815886.38     10297321.92
      2814905.65     10297953.13
#Sta/Elev= 30
  4575.1 1393.44  4635.9 1394.79    4717 1393.72  4747.4 1391.03  4879.1  1384.5
  4939.9 1380.22  4970.3 1374.91  4975.9 1372.63  4990.6 1372.39  4992.9 1371.26
  4993.4 1370.76  5002.8 1371.26  5030.2 1373.19  5036.5 1375.11  5072.5  1378.6
    5203 1378.42  5326.7 1380.94  5420.5  1384.1  5544.6 1390.94  5631.1 1394.34
  5674.7 1398.11  5892.6 1408.38  5898.5 1411.42  5913.7 1409.41  5971.1 1412.67
  6022.6 1415.98  6064.9 1420.33  6080.1 1420.18  6107.2 1424.24  6166.3 1428.64
#Mann= 3 ,-1 , 0
  4575.1     .05       0  4992.9     .05       0  5002.8     .05       0
Bank Sta=4992.9,5002.8
XS Rating Curve= 0 ,0
Exp/Cntr=0.3,0.1

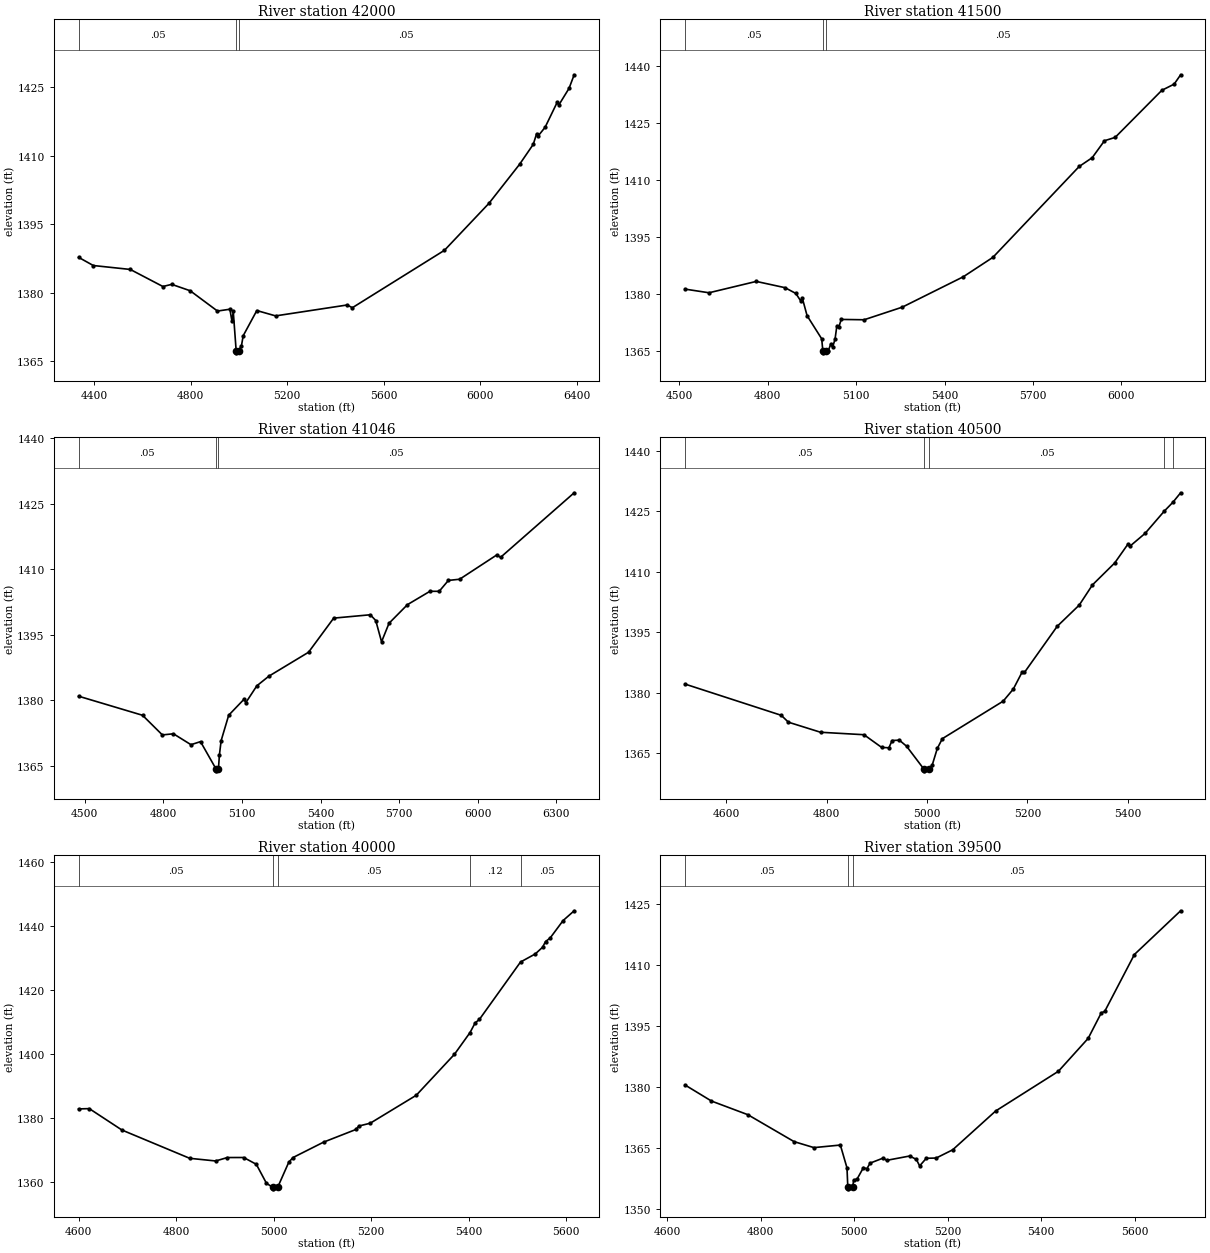
Type RM Length L Ch R = 1 ,42000   ,500,500,500
BEGIN DESCRIPTION:
BABYHEAD CREEK 84.0
END DESCRIPTION:
XS GIS Cut Line= 3
      2816404.75     10296999.87      2815759.04      10296842.1
      2814755.71     10297803.08
#Sta/Elev= 30
  4335.3 1387.73  4396.1 1385.94  4549.4 1385.08  4684.6 1381.34  4721.1 1381.81
  4797.6 1380.41  4910.8 1375.96  4962.3 1376.36    4971 1373.68  4976.2 1375.89
  4988.2  1367.3  4988.7  1366.8  4998.1  1367.3  5010.1 1368.32  5017.4 1370.55
  5073.9 1376.07  5151.7  1374.9  5448.5 1377.29  5469.9 1376.69  5851.7 1389.28
  6035.7 1399.55  6163.1 1408.13  6219.7  1412.5  6233.8 1414.85  6240.7 1414.38
    6269 1416.26  6318.7 1421.69  6325.7 1421.13  6368.1 1424.78  6389.3 1427.75
#Mann= 3 ,-1 , 0
  4335.3     .05       0  4988.2     .03       0  4998.1     .05       0
Bank Sta=4988.2,4998.1
XS Rating Curve= 0 ,0
Exp/Cntr=0.3,0.1

Type RM Length L Ch R = 1 ,41500   ,454,454,454
BEGIN DESCRIPTION:
BABYHEAD CREEK 83.0
END DESCRIPTION:
XS GIS Cut Line= 4
      2815736.28     10296665.68      2815429.18     10296802.78
      2815361.17     10296930.27       2814655.7     10297903.09
#Sta/Elev= 30
  4519.2  1381.2  4600.4 1380.24  4760.8 1383.23  4858.5 1381.58  4895.2 1380.06
  4911.5 1378.13  4917.1 1378.87  4933.4  1374.2    4983 1368.11  4986.9 1364.92
  4987.4 1364.42  4996.8 1364.92  5005.3 1364.99  5013.8  1366.7    5020 1365.91
  5028.2 1367.97  5034.6 1371.58  5040.8 1371.12  5049.3 1373.22    5127 1373.13
  5256.5 1376.45  5463.7 1384.45  5564.3 1389.57  5857.3  1413.5  5901.4 1415.81
  5943.1 1420.28  5979.4 1421.16  6137.9 1433.56  6179.7 1435.19  6201.7 1437.65
#Mann= 3 ,-1 , 0
  4519.2     .05       0  4986.9     .03       0  4996.8     .05       0
Bank Sta=4986.9,4996.8
XS Rating Curve= 0 ,0
Exp/Cntr=0.3,0.1

Type RM Length L Ch R = 1 ,41046   ,546,546,546
BEGIN DESCRIPTION:
Mapping XS 625bccc1
END DESCRIPTION:
XS GIS Cut Line= 4
      2815407.32     10296771.87      2815146.93     10296806.59
      2814547.97     10297188.53      2813845.24     10297778.48
#Sta/Elev= 30
    4477  1380.9  4720.8 1376.53  4796.4 1372.03  4838.7 1372.29  4905.6 1369.79
    4942 1370.49  5000.5  1364.3    5001  1363.8  5010.5  1364.3    5014 1367.39
  5020.7 1370.72  5049.5 1376.54  5108.7 1380.25  5114.6  1379.4  5156.9 1383.28
  5202.6 1385.48  5354.1 1390.97  5450.1 1398.79  5589.8 1399.56  5610.6 1398.24
  5632.7 1393.37  5661.3 1397.62  5731.6 1401.88  5817.4 1404.94  5852.5 1404.93
  5887.7 1407.43  5930.6  1407.7  6072.4 1413.27  6086.7 1412.71  6367.6 1427.51
#Mann= 3 ,-1 , 0
    4477     .05       0  5000.5     .03       0  5010.5     .05       0
Bank Sta=5000.5,5010.5
XS Rating Curve= 0 ,0
Exp/Cntr=0.3,0.1

Type RM Length L Ch R = 1 ,40500   ,500,500,500
BEGIN DESCRIPTION:
BABYHEAD CREEK 81.0
END DESCRIPTION:
XS GIS Cut Line= 3
      2815455.72     10296753.14      2815078.05     10296453.18
      2815005.68     10295953.08
#Sta/Elev= 30
  4517.7  1382.1  4709.3 1374.35  4723.6 1372.64  4787.7 1370.14  4874.2 1369.53
  4909.5 1366.37  4923.9 1366.29  4930.3 1368.09  4944.7 1368.18  4959.1 1366.67
  4993.2 1361.06  4993.7 1360.56  5003.5 1361.06  5010.2 1361.99  5020.3 1366.11
  5030.4 1368.55  5151.6 1377.86  5171.8 1380.86    5189 1384.99  5194.1 1385.01
  5259.3 1396.45  5303.2 1401.72  5329.6 1406.74  5373.9 1412.18  5399.9 1416.79
  5404.9 1416.41  5434.5 1419.53  5472.9 1425.08  5489.9 1427.25  5505.3 1429.61
#Mann= 5 ,-1 , 0
  4517.7     .05       0  4993.2     .05       0  5003.5     .05       0
  5472.9     .12       0  5489.9     .05       0
Bank Sta=4993.2,5003.5
XS Rating Curve= 0 ,0
Exp/Cntr=0.3,0.1

Type RM Length L Ch R = 1 ,40000   ,500,500,500
BEGIN DESCRIPTION:
BABYHEAD CREEK 80.0
END DESCRIPTION:
XS GIS Cut Line= 3
      2815605.67     10296703.08      2815493.43     10296318.73
      2815155.68      10295803.1
#Sta/Elev= 30
  4599.6 1382.81  4621.5  1382.9  4688.4 1376.22  4827.5 1367.39  4880.8 1366.56
  4904.8 1367.63  4938.3 1367.64  4964.2 1365.52    4985 1359.59  4997.6 1358.36
  4998.1 1357.86  5008.1 1358.36  5030.6  1366.1  5039.1  1367.6  5102.4 1372.45
  5168.7  1376.4  5174.7 1377.47    5198 1378.35  5292.3 1387.06  5370.7 1399.85
  5402.7 1406.64  5413.2 1409.66    5422 1410.76  5506.3 1428.66  5536.5 1431.18
  5551.6 1433.28  5557.6 1435.07  5566.7 1436.08  5593.7 1441.61  5616.4 1444.66
#Mann= 5 ,-1 , 0
  4599.6     .05       0  4997.6     .05       0  5008.1     .05       0
  5402.7     .12       0  5506.3     .05       0
Bank Sta=4997.6,5008.1
XS Rating Curve= 0 ,0
Exp/Cntr=0.3,0.1

Type RM Length L Ch R = 1 ,39500   ,500,500,500
BEGIN DESCRIPTION:
BABYHEAD CREEK 79.0
END DESCRIPTION:
XS GIS Cut Line= 3
      2816205.67      10296403.1      2815949.83     10296147.13
      2815455.71     10295653.14
#Sta/Elev= 30
  4638.1 1380.43  4694.6 1376.49  4772.4 1373.14  4871.4 1366.52  4913.9 1365.05
  4970.4 1365.68  4984.6 1360.07  4986.3 1355.42  4986.8 1354.92    4997 1355.42
  4998.7    1357  5006.4 1357.37  5019.9 1360.16    5027 1359.83  5034.1 1361.24
  5062.3 1362.49  5069.4 1361.92  5118.9 1362.99  5133.1 1362.14  5140.1 1360.55
  5154.3 1362.43  5175.5 1362.49  5210.8 1364.51  5302.8 1374.05  5437.1 1383.81
  5500.8  1391.9    5529 1398.19  5536.1  1398.5  5599.7  1412.5  5698.7 1423.25
#Mann= 3 ,-1 , 0
  4638.1     .05       0  4986.3     .05       0    4997     .05       0
Bank Sta=4986.3,4997
XS Rating Curve= 0 ,0
Exp/Cntr=0.3,0.1