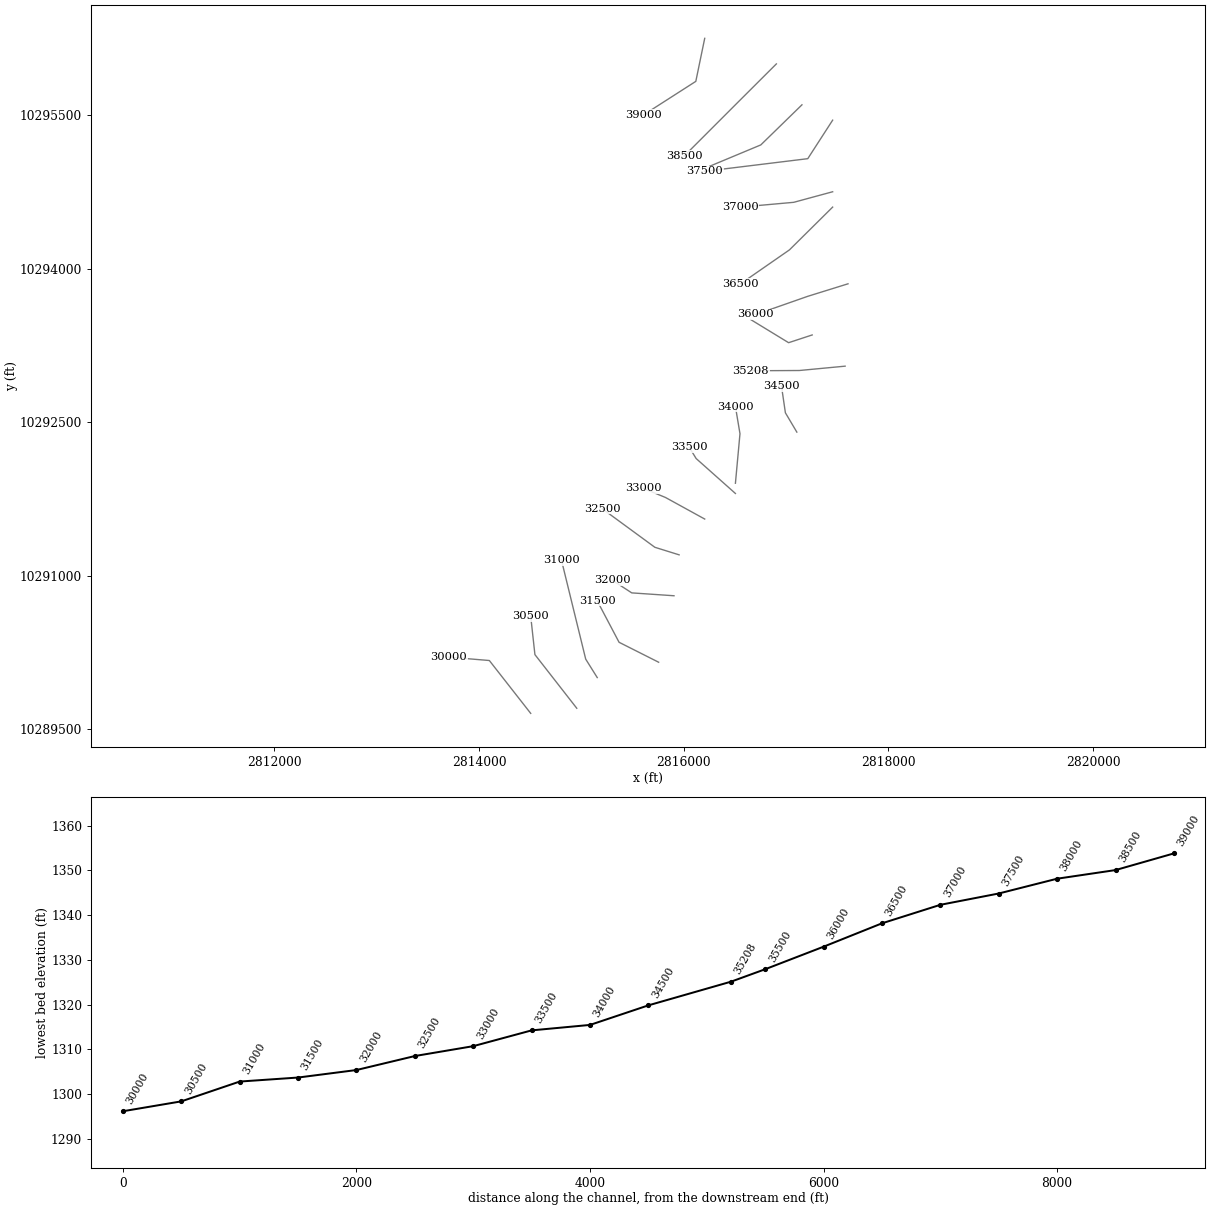
HEC-RAS study BABYHEAD CREEK.prj: BABYHEAD CREEK Base Level Engineering

--- BABYHEAD CREEK.g01 (geometry) --- (continued)

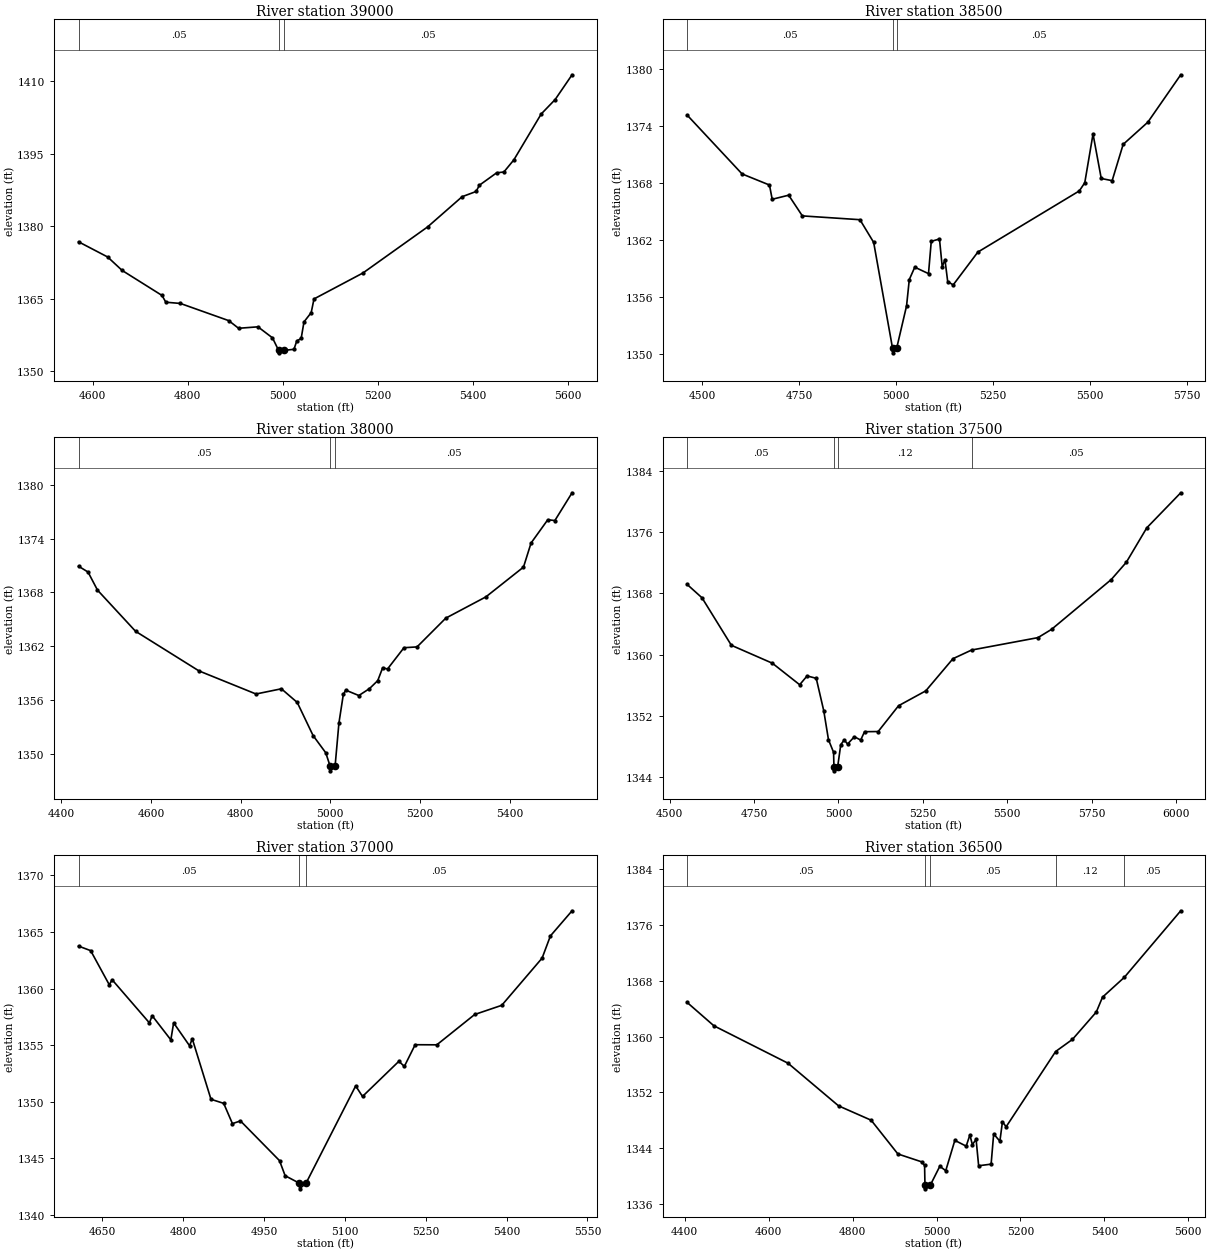
Type RM Length L Ch R = 1 ,39000   ,500,500,500
BEGIN DESCRIPTION:
BABYHEAD CREEK 78.0
END DESCRIPTION:
XS GIS Cut Line= 3
      2816205.68     10296253.11      2816118.75     10295832.39
      2815605.72     10295503.14
#Sta/Elev= 30
  4570.4 1376.78  4631.7 1373.64  4662.3 1370.85  4746.2 1365.68  4754.2 1364.28
  4784.8 1364.03  4886.7 1360.47  4907.4 1358.89  4948.2 1359.19  4978.8 1356.91
  4991.7 1354.31  4992.2 1353.81  5002.4 1354.31    5024 1354.54  5029.9 1356.26
  5039.2  1356.8  5045.1 1360.21  5060.3 1362.13  5066.2 1364.96  5169.3 1370.33
  5305.4 1379.86  5378.1 1386.11  5407.6 1387.19  5414.4 1388.48  5450.8 1391.05
    5466 1391.22  5487.1 1393.74  5544.6 1403.22    5574 1406.21  5609.6 1411.33
#Mann= 3 ,-1 , 0
  4570.4     .05       0  4991.7     .05       0  5002.4     .05       0
Bank Sta=4991.7,5002.4
XS Rating Curve= 0 ,0
Exp/Cntr=0.3,0.1

Type RM Length L Ch R = 1 ,38500   ,500,500,500
BEGIN DESCRIPTION:
BABYHEAD CREEK 77.0
END DESCRIPTION:
XS GIS Cut Line= 3
      2816905.71     10296003.14      2816524.33     10295622.41
      2816005.71     10295103.14
#Sta/Elev= 30
  4461.1 1375.11  4602.6 1368.92  4673.3 1367.75  4680.3 1366.25  4722.8 1366.68
  4758.1  1364.5  4906.6  1364.1    4942 1361.71  4990.6 1350.58  4991.1 1350.08
  5001.4 1350.58  5026.8 1355.02  5033.9  1357.8    5048  1359.1  5083.4 1358.42
  5090.5 1361.82  5111.7 1362.07  5118.8 1359.14  5125.8  1359.9  5132.9 1357.59
    5147 1357.23  5210.7 1360.69  5472.3 1367.13  5486.4 1367.99  5507.7 1373.12
  5528.9 1368.44    5557 1368.21  5585.4 1372.03  5649.1 1374.37  5733.9 1379.36
#Mann= 3 ,-1 , 0
  4461.1     .05       0  4990.6     .05       0  5001.4     .05       0
Bank Sta=4990.6,5001.4
XS Rating Curve= 0 ,0
Exp/Cntr=0.3,0.1

Type RM Length L Ch R = 1 ,38000   ,500,500,500
BEGIN DESCRIPTION:
BABYHEAD CREEK 76.0
END DESCRIPTION:
XS GIS Cut Line= 3
      2817155.68      10295603.1      2816753.62     10295211.01
      2816255.67     10295003.11
#Sta/Elev= 30
  4438.4 1370.92  4459.6 1370.27  4480.7 1368.26  4565.6 1363.68  4707.1 1359.27
  4834.4  1356.7    4891 1357.28  4926.4 1355.76  4961.7 1352.08    4990 1350.16
  4999.9 1348.65  5000.4 1348.15  5010.8 1348.65  5019.4 1353.47  5029.2 1356.65
  5034.6 1357.13  5063.8 1356.53  5087.6  1357.3    5106 1358.19    5117 1359.62
  5127.8 1359.48  5164.5 1361.85  5193.7 1361.94  5257.8 1365.14  5347.4 1367.51
  5431.2 1370.82  5448.1  1373.5  5485.4 1376.09  5501.2    1376  5539.6 1379.09
#Mann= 3 ,-1 , 0
  4438.4     .05       0  4999.9     .05       0  5010.8     .05       0
Bank Sta=4999.9,5010.8
XS Rating Curve= 0 ,0
Exp/Cntr=0.3,0.1

Type RM Length L Ch R = 1 ,37500   ,500,500,500
BEGIN DESCRIPTION:
BABYHEAD CREEK 75.0
END DESCRIPTION:
XS GIS Cut Line= 3
      2817455.67     10295453.09      2817212.55     10295076.56
      2816205.69     10294953.11
#Sta/Elev= 30
  4551.8 1369.17  4595.7 1367.43  4682.7 1361.23  4804.2 1358.89  4885.1 1356.08
  4907.1 1357.23  4934.2 1356.92  4956.5 1352.68  4970.5  1348.9  4985.6 1347.26
  4986.7 1345.34  4987.2 1344.84  4997.6 1345.34  5006.9 1348.25    5017 1348.87
  5027.1 1348.34  5047.2 1349.29  5065.9 1348.86  5077.4 1349.95  5117.7 1349.97
  5178.2 1353.34  5258.8 1355.28  5339.4 1359.48  5394.6 1360.61  5591.3 1362.23
  5631.6 1363.31  5808.4 1369.81  5853.2 1372.07  5913.7 1376.56  6014.4 1381.14
#Mann= 4 ,-1 , 0
  4551.8     .05       0  4986.7     .07       0  4997.6     .12       0
  5394.6     .05       0
Bank Sta=4986.7,4997.6
XS Rating Curve= 0 ,0
Exp/Cntr=0.3,0.1

Type RM Length L Ch R = 1 ,37000   ,500,500,500
BEGIN DESCRIPTION:
BABYHEAD CREEK 74.0
END DESCRIPTION:
XS GIS Cut Line= 3
      2817455.69     10294753.11      2817075.17     10294649.78
      2816555.66     10294603.11
#Sta/Elev= 30
  4605.7 1363.75  4628.2 1363.35  4662.8 1360.33    4668 1360.78  4737.2 1356.97
  4742.4  1357.6    4777 1355.47  4782.2 1356.97  4811.7 1354.95  4816.8 1355.56
  4851.5 1350.22  4875.1 1349.86  4891.3 1348.07  4906.2 1348.31  4978.7  1344.8
  4989.1 1343.47  5015.4 1342.81  5015.9 1342.31  5027.9 1342.81    5120  1351.4
  5132.7 1350.47  5200.3 1353.58  5210.3 1353.12  5230.4 1355.04  5270.6 1355.03
  5340.9 1357.71  5391.1 1358.52    5466 1362.69  5481.4 1364.65  5521.6 1366.87
#Mann= 3 ,-1 , 0
  4605.7     .05       0  5015.4     .05       0  5027.9     .05       0
Bank Sta=5015.4,5027.9
XS Rating Curve= 0 ,0
Exp/Cntr=0.3,0.1

Type RM Length L Ch R = 1 ,36500   ,500,500,500
BEGIN DESCRIPTION:
BABYHEAD CREEK 73.0
END DESCRIPTION:
XS GIS Cut Line= 3
      2817455.65     10294603.08      2817033.74     10294184.96
      2816555.72     10293853.14
#Sta/Elev= 30
    4406 1364.89  4469.6 1361.55  4646.3 1356.18  4766.6 1350.07  4844.3 1348.01
    4908 1343.17  4964.6 1342.04  4971.6 1341.53  4972.5 1338.67    4973 1338.17
    4985 1338.67  5007.9 1341.41    5022 1340.77  5043.7 1345.12  5070.7 1344.29
  5079.5 1345.89  5085.5  1344.5  5094.3 1345.28  5100.4 1341.48  5130.1 1341.71
  5136.2 1346.04    5151    1345  5157.1 1347.78  5165.9 1347.07  5283.8 1357.86
  5323.9  1359.6  5380.7 1363.52  5395.5 1365.65  5447.7 1368.51  5581.9 1378.04
#Mann= 5 ,-1 , 0
    4406     .05       0  4972.5     .05       0    4985     .05       0
  5283.8     .12       0  5447.7     .05       0
Bank Sta=4972.5,4985
XS Rating Curve= 0 ,0
Exp/Cntr=0.3,0.1

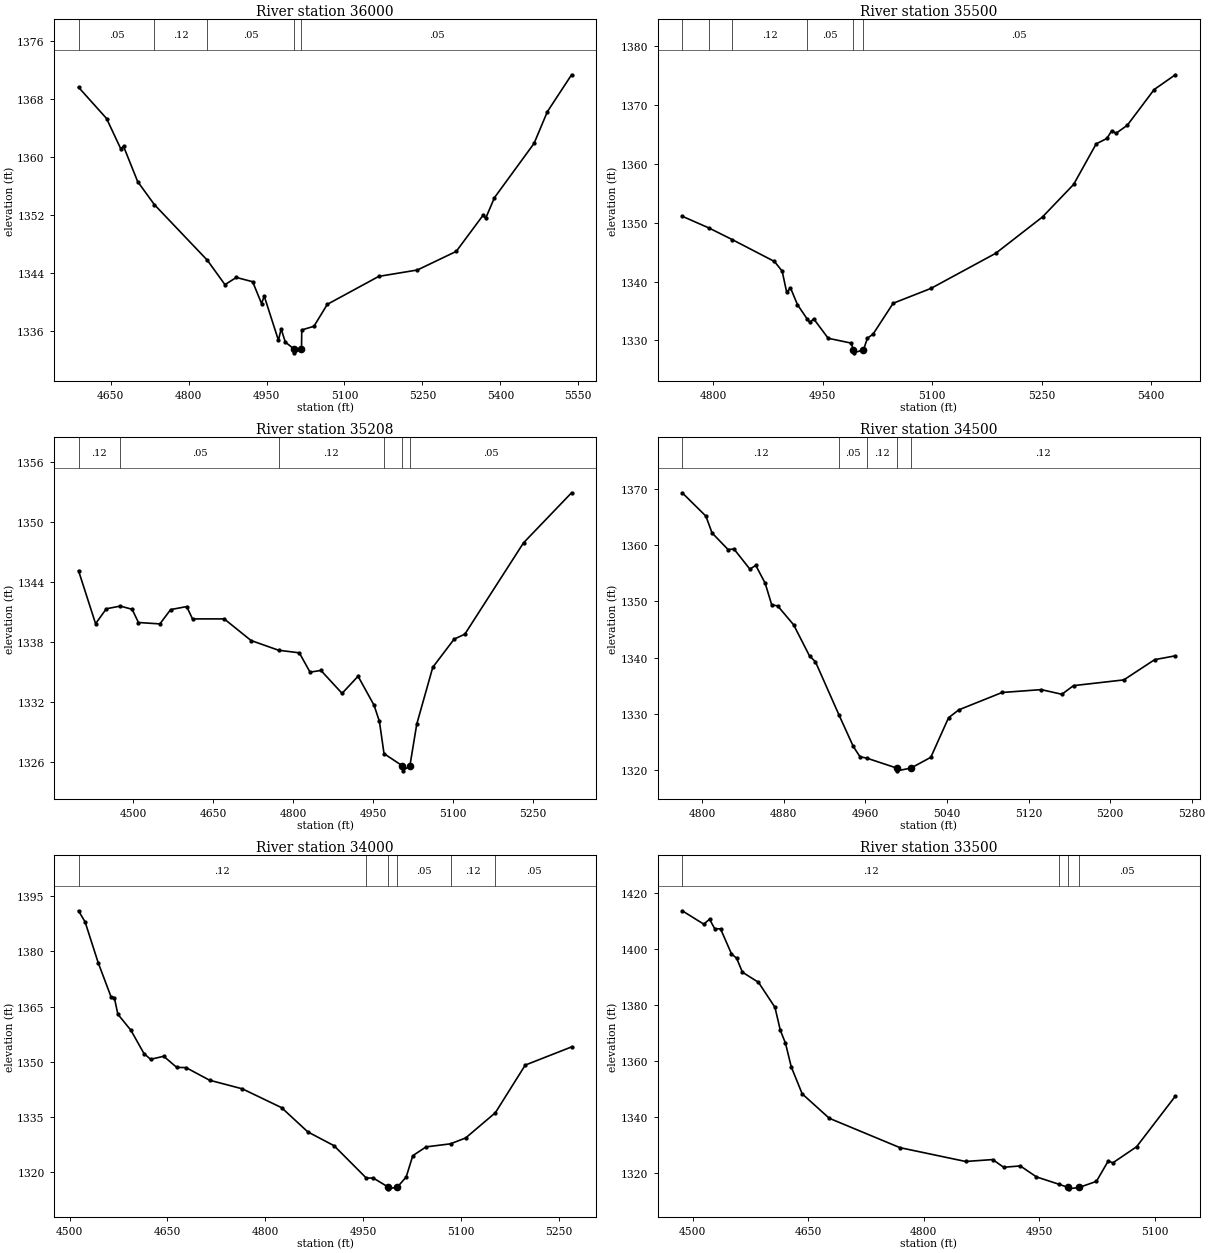
Type RM Length L Ch R = 1 ,36000   ,500,500,500
BEGIN DESCRIPTION:
BABYHEAD CREEK 72.0
END DESCRIPTION:
XS GIS Cut Line= 3
      2817605.67     10293853.11      2817212.44     10293730.81
       2816705.7     10293553.12
#Sta/Elev= 30
  4588.2 1369.62  4642.2  1365.3  4669.5 1361.12  4674.8 1361.47  4702.1 1356.58
  4734.2 1353.41  4836.2 1345.72    4870 1342.36  4891.9 1343.35  4923.3 1342.76
  4940.4 1339.75  4945.6 1340.77  4972.9 1334.68  4978.2 1336.24  4986.1 1334.43
  5003.3 1333.44  5003.8 1332.94  5017.3 1333.44  5017.8  1336.1  5041.3 1336.61
    5067 1339.64  5166.1  1343.5  5240.3 1344.38  5315.1 1346.95  5366.5 1351.92
  5371.8 1351.54  5388.7 1354.38  5464.8 1361.86  5490.5 1366.25    5537 1371.34
#Mann= 5 ,-1 , 0
  4588.2     .05       0  4734.2     .12       0  4836.2     .05       0
  5003.3     .05       0  5017.3     .05       0
Bank Sta=5003.3,5017.3
XS Rating Curve= 0 ,0
Exp/Cntr=0.3,0.1

Type RM Length L Ch R = 1 ,35500   ,292,292,292
BEGIN DESCRIPTION:
BABYHEAD CREEK 71.0
END DESCRIPTION:
XS GIS Cut Line= 3
      2817255.69     10293353.11      2817025.33     10293277.35
      2816655.72     10293503.09
#Sta/Elev= 30
  4757.5 1351.07  4794.1 1349.08    4826 1347.11  4883.8  1343.4  4894.4 1341.77
  4900.6 1338.18  4905.8 1338.93  4915.4 1336.07  4928.6 1333.66  4932.4 1333.06
  4937.6 1333.67  4957.5 1330.37  4989.1 1329.55  4991.8  1328.4  4992.3  1327.9
  5005.8  1328.4  5011.3  1330.4  5018.9 1331.06  5046.5 1336.31  5098.3 1338.83
  5187.1 1344.79  5251.2 1350.96  5293.8 1356.47  5324.7 1363.35  5339.4 1364.27
    5346 1365.59  5351.9 1365.14  5367.3  1366.5  5404.1 1372.56  5433.1 1375.07
#Mann= 6 ,-1 , 0
  4757.5     .12       0  4794.1     .05       0    4826     .12       0
  4928.6     .05       0  4991.8     .05       0  5005.8     .05       0
Bank Sta=4991.8,5005.8
XS Rating Curve= 0 ,0
Exp/Cntr=0.3,0.1

Type RM Length L Ch R = 1 ,35208   ,708,708,708
BEGIN DESCRIPTION:
BABYHEAD CREEK 70.0
END DESCRIPTION:
XS GIS Cut Line= 3
       2817577.5     10293047.91      2817129.86      10293005.4
      2816655.72     10293003.11
#Sta/Elev= 30
  4397.9 1345.12  4429.9 1339.82    4450 1341.31  4476.2 1341.58  4498.3 1341.26
  4510.2 1339.94  4550.4  1339.8  4570.5 1341.23  4600.6 1341.53  4611.5  1340.3
  4670.9  1340.3  4721.2 1338.14  4772.7 1337.17  4811.6 1336.91  4831.7 1334.98
  4852.1 1335.15  4891.7 1332.86  4921.7 1334.57  4951.7 1331.67  4961.7 1330.05
  4970.3 1326.84  5004.7 1325.62  5005.2 1325.12  5018.8 1325.62  5031.7  1329.8
  5061.7 1335.47  5101.7 1338.28  5121.7 1338.77  5231.7  1347.9  5321.7  1352.9
#Mann= 6 ,-1 , 0
  4397.9     .12       0  4476.2     .05       0  4772.7     .12       0
  4970.3     .05       0  5004.7     .05       0  5018.8     .05       0
Bank Sta=5004.7,5018.8
XS Rating Curve= 0 ,0
Exp/Cntr=0.3,0.1

Type RM Length L Ch R = 1 ,34500   ,500,500,500
BEGIN DESCRIPTION:
BABYHEAD CREEK 69.0
END DESCRIPTION:
XS GIS Cut Line= 3
      2817105.68     10292403.11      2816993.87       10292592.
      2816955.68     10292853.12
#Sta/Elev= 30
  4780.5 1369.36  4803.7  1365.2  4809.7 1362.21  4825.4 1359.25  4831.2 1359.35
  4846.8 1355.76  4852.6 1356.42  4861.8 1353.25  4868.2 1349.41  4874.1  1349.2
  4889.7 1345.84  4905.3 1340.29  4911.1 1339.25    4934 1329.85  4948.2 1324.16
  4954.8 1322.33  4961.5 1322.08  4990.7 1320.32  4991.2 1319.82  5004.8 1320.32
  5024.2 1322.23  5041.6 1329.28  5051.7 1330.69  5094.1 1333.78  5132.5 1334.29
  5152.7 1333.46  5164.1    1335  5213.4 1336.02  5243.7 1339.63  5263.9 1340.31
#Mann= 5 ,-1 , 0
  4780.5     .12       0    4934     .05       0  4961.5     .12       0
  4990.7     .07       0  5004.8     .12       0
Bank Sta=4990.7,5004.8
XS Rating Curve= 0 ,0
Exp/Cntr=0.3,0.1

Type RM Length L Ch R = 1 ,34000   ,500,500,500
BEGIN DESCRIPTION:
BABYHEAD CREEK 68.0
END DESCRIPTION:
XS GIS Cut Line= 3
      2816505.68      10291903.1      2816550.22     10292387.46
      2816505.68     10292653.15
#Sta/Elev= 30
  4513.6 1391.03  4523.7    1388  4543.7 1376.95  4563.5 1367.62  4568.5 1367.43
  4573.9 1362.91  4593.9 1358.55    4614 1352.21  4624.1 1350.65  4644.2 1351.48
  4664.2 1348.45  4678.4  1348.4  4714.5 1344.97  4764.7 1342.63  4824.9 1337.51
  4865.1 1330.92  4905.3 1327.17  4954.7 1318.38  4965.5 1318.37  4988.2 1315.94
  4988.7 1315.44  5002.5 1315.94  5015.9 1318.66    5026 1324.45  5046.3 1326.84
  5083.9 1327.68  5107.1 1329.28  5152.6 1336.13  5198.4 1349.08  5269.4 1354.02
#Mann= 6 ,-1 , 0
  4513.6     .12       0  4954.7     .05       0  4988.2     .05       0
  5002.5     .05       0  5083.9     .12       0  5152.6     .05       0
Bank Sta=4988.2,5002.5
XS Rating Curve= 0 ,0
Exp/Cntr=0.3,0.1

Type RM Length L Ch R = 1 ,33500   ,500,500,500
BEGIN DESCRIPTION:
BABYHEAD CREEK 67.0
END DESCRIPTION:
XS GIS Cut Line= 3
      2816505.69      10291803.1      2816121.96     10292144.78
      2816055.68     10292253.11
#Sta/Elev= 30
  4486.2 1413.49  4514.2 1408.71  4521.7 1410.48  4528.4 1407.09    4536 1407.03
  4550.2 1398.11  4556.9 1396.55  4564.4 1391.57  4585.3 1387.94  4606.7 1379.02
  4613.7 1370.81  4620.4 1366.19  4627.9 1357.75  4642.1 1348.13  4677.3 1339.41
  4769.2 1328.92  4854.5 1323.99  4889.7 1324.67  4903.9 1321.92  4925.6  1322.4
  4946.5 1318.49  4975.5 1315.88  4987.8 1314.72  4988.3 1314.22  5002.1 1314.72
  5024.5 1316.89  5039.9 1324.19  5045.8 1323.49  5076.7 1329.25    5127 1347.29
#Mann= 4 ,-1 , 0
  4486.2     .12       0  4975.5     .05       0  4987.8     .05       0
  5002.1     .05       0
Bank Sta=4987.8,5002.1
XS Rating Curve= 0 ,0
Exp/Cntr=0.3,0.1

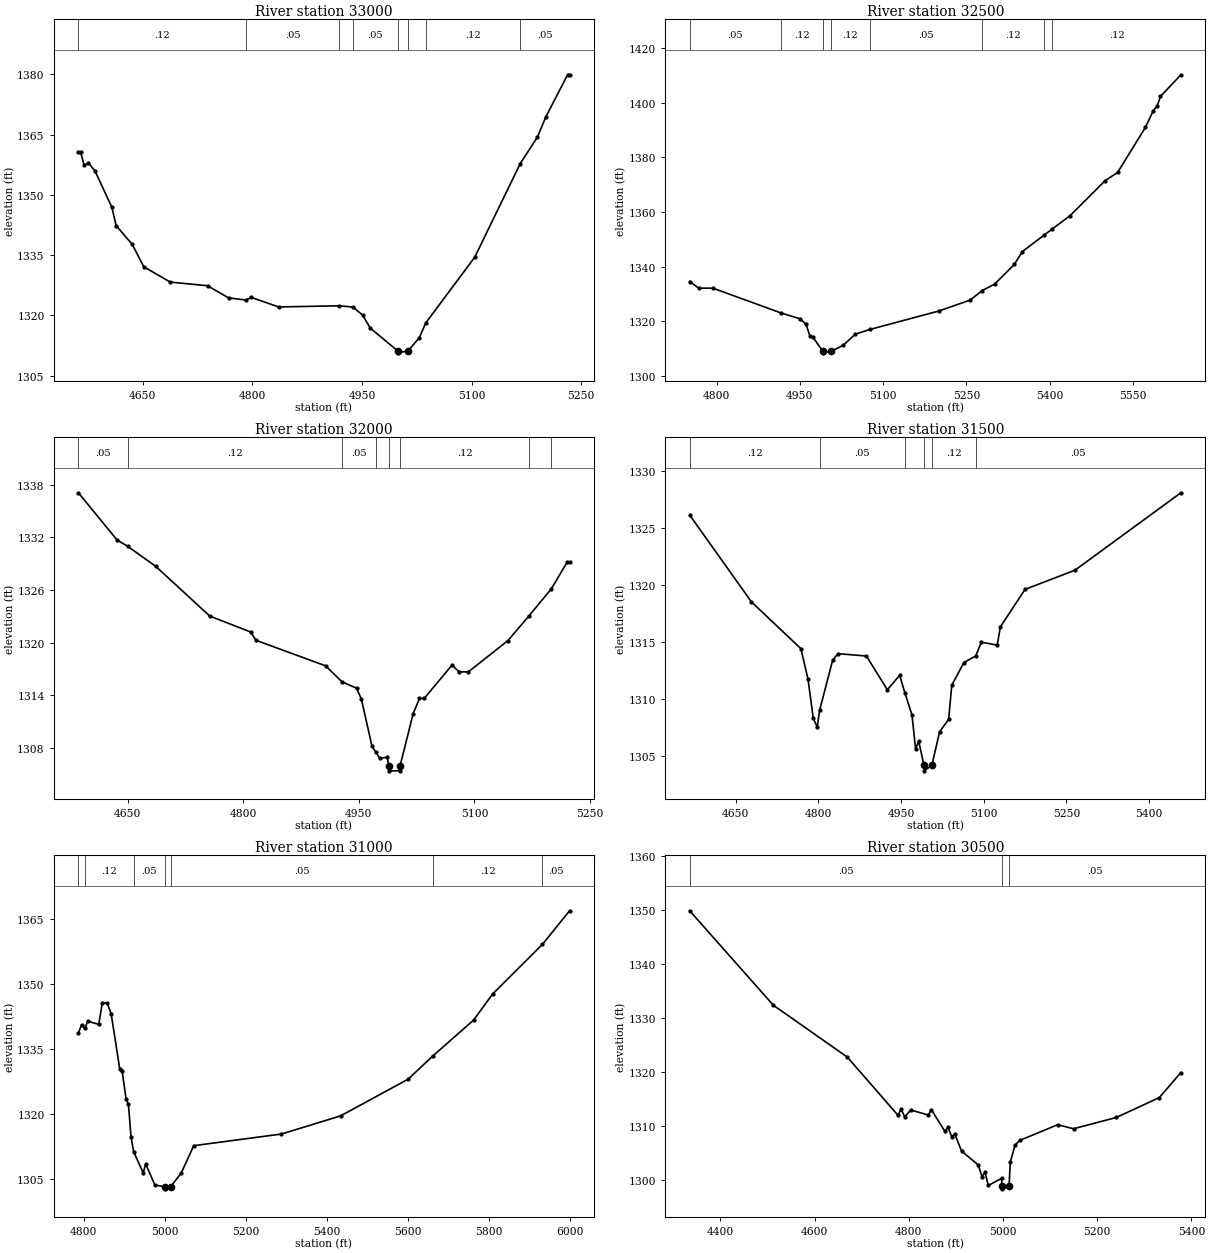
Type RM Length L Ch R = 1 ,33000   ,500,500,500
BEGIN DESCRIPTION:
BABYHEAD CREEK 66.0
END DESCRIPTION:
XS GIS Cut Line= 3
      2816205.68     10291553.11      2815822.11     10291764.16
      2815605.68     10291853.11
#Sta/Elev= 30
  4562.2 1360.65  4565.1 1360.65  4570.2 1357.32  4575.9 1357.95    4585 1355.91
  4607.9 1346.92  4613.8 1342.36  4635.6 1337.73  4651.7 1332.11  4687.7  1328.3
  4738.8 1327.39  4767.6 1324.37  4791.3 1323.83  4798.5 1324.49  4836.1 1322.11
  4918.8  1322.4  4937.7 1322.08    4951 1320.06  4961.3 1316.86  4998.8 1311.19
  4999.3 1310.69  5013.2 1311.19  5028.6 1314.49  5037.2 1318.11  5104.3 1334.49
  5166.6 1357.81  5189.9 1364.34  5201.6 1369.44  5231.3 1379.89    5234 1379.89
#Mann= 8 ,-1 , 0
  4562.2     .12       0  4791.3     .05       0  4918.8     .12       0
  4937.7     .05       0  4998.8     .03       0  5013.2     .05       0
  5037.2     .12       0  5166.6     .05       0
Bank Sta=4998.8,5013.2
XS Rating Curve= 0 ,0
Exp/Cntr=0.3,0.1

Type RM Length L Ch R = 1 ,32500   ,500,500,500
BEGIN DESCRIPTION:
BABYHEAD CREEK 65.0
END DESCRIPTION:
XS GIS Cut Line= 3
      2815955.69     10291203.11      2815718.65     10291277.02
      2815205.66     10291653.13
#Sta/Elev= 30
  4751.7 1334.58    4768 1332.16  4793.6 1332.15  4916.1 1323.08  4950.7 1320.92
  4961.2 1318.93  4968.3 1314.56  4973.5 1314.25  4991.7 1308.98  4992.2 1308.48
  5006.1 1308.98  5028.5 1311.29  5049.8  1315.3    5076 1317.03  5200.3 1323.79
  5256.7 1327.79  5278.3 1331.27  5300.7 1333.63  5336.2 1340.82  5350.8 1345.57
  5389.9 1351.59  5404.8 1353.86  5436.5 1358.67  5499.7  1371.5  5522.2  1374.5
  5572.4 1391.07  5586.5 1397.16  5593.2 1398.73  5599.4 1402.33  5636.1 1410.27
#Mann= 8 ,-1 , 0
  4751.7     .05       0  4916.1     .12       0  4991.7     .07       0
  5006.1     .12       0    5076     .05       0  5278.3     .12       0
  5389.9     .05       0  5404.8     .12       0
Bank Sta=4991.7,5006.1
XS Rating Curve= 0 ,0
Exp/Cntr=0.3,0.1

Type RM Length L Ch R = 1 ,32000   ,500,500,500
BEGIN DESCRIPTION:
BABYHEAD CREEK 64.0
END DESCRIPTION:
XS GIS Cut Line= 3
      2815905.69     10290803.11      2815492.85     10290831.19
      2815305.66     10290953.13
#Sta/Elev= 30
  4586.2  1337.1  4636.3 1331.71    4650 1330.99  4686.4 1328.71  4756.6 1323.02
  4809.5 1321.21  4816.7 1320.25  4906.9 1317.34  4928.2 1315.51    4947 1314.79
  4953.3 1313.55  4967.1 1308.15  4971.8 1307.51  4977.1 1306.79  4987.1 1306.89
  4988.8 1305.85  4989.3 1305.35  5002.8 1305.35  5003.3 1305.85  5020.5 1311.89
  5028.7 1313.61  5034.7 1313.61  5070.9 1317.42  5080.1 1316.65  5092.1 1316.65
  5143.4 1320.22  5170.9 1323.06  5199.8 1326.14  5220.4 1329.19  5223.4 1329.19
#Mann= 8 ,-1 , 0
  4586.2     .05       0    4650     .12       0  4928.2     .05       0
  4971.8     .12       0  4988.8     .07       0  5003.3     .12       0
  5170.9     .05       0  5199.8     .12       0
Bank Sta=4988.8,5003.3
XS Rating Curve= 0 ,0
Exp/Cntr=0.3,0.1

Type RM Length L Ch R = 1 ,31500   ,500,500,500
BEGIN DESCRIPTION:
BABYHEAD CREEK 63.0
END DESCRIPTION:
XS GIS Cut Line= 3
      2815755.66     10290153.12       2815368.9     10290348.26
      2815155.67     10290753.15
#Sta/Elev= 30
  4566.8 1326.15  4678.8 1318.52  4768.4 1314.41  4781.4 1311.72  4790.8 1308.31
  4798.1 1307.51  4802.4 1308.99    4826 1313.38  4835.6 1313.97  4887.3 1313.76
  4925.2  1310.8  4947.6 1312.06  4957.2  1310.5    4970 1308.58  4976.5 1305.59
  4982.1 1306.28  4991.6 1304.17  4992.1 1303.67  5006.1 1304.17    5020  1307.1
  5036.4 1308.19  5042.1 1311.19  5064.1 1313.19  5085.4 1313.76  5095.9 1314.98
  5124.5 1314.72  5130.2 1316.32    5175 1319.62  5265.4  1321.3  5457.6 1328.11
#Mann= 6 ,-1 , 0
  4566.8     .12       0  4802.4     .05       0  4957.2     .12       0
  4991.6     .07       0  5006.1     .12       0  5085.4     .05       0
Bank Sta=4991.6,5006.1
XS Rating Curve= 0 ,0
Exp/Cntr=0.3,0.1

Type RM Length L Ch R = 1 ,31000   ,500,500,500
BEGIN DESCRIPTION:
BABYHEAD CREEK 62.0
END DESCRIPTION:
XS GIS Cut Line= 3
      2815155.69      10290003.1      2815043.03     10290183.39
      2814805.69     10291153.07
#Sta/Elev= 30
  4787.4 1338.73  4795.1 1340.65  4803.3 1339.83  4810.4 1341.48  4837.5 1340.77
  4846.4 1345.78  4858.8 1345.62  4868.2 1343.18  4889.4  1330.4  4895.3 1329.95
  4904.8 1323.57  4910.7 1322.33  4917.1 1314.75  4923.7  1311.3  4947.2 1306.44
  4953.1  1308.5  4976.1 1303.64  4999.9 1303.27  5000.4 1302.77  5014.9 1303.27
  5040.9 1306.43  5071.8 1312.74    5288 1315.43  5433.9 1319.63  5600.4  1328.1
  5661.8 1333.52  5761.6 1341.74  5808.5 1347.76  5931.5 1359.25  5998.3    1367
#Mann= 7 ,-1 , 0
  4787.4     .05       0  4803.3     .12       0  4923.7     .05       0
  4999.9     .03       0  5014.9     .05       0  5661.8     .12       0
  5931.5     .05       0
Bank Sta=4999.9,5014.9
XS Rating Curve= 0 ,0
Exp/Cntr=0.3,0.1

Type RM Length L Ch R = 1 ,30500   ,500,500,500
BEGIN DESCRIPTION:
BABYHEAD CREEK 61.0
END DESCRIPTION:
XS GIS Cut Line= 3
       2814955.7     10289703.09      2814546.83     10290227.67
      2814505.68     10290603.12
#Sta/Elev= 30
  4334.9 1349.85  4512.4 1332.36  4669.6 1322.74  4777.3 1311.95  4783.6 1313.12
  4791.4 1311.68  4804.4 1312.95  4841.5 1312.01  4847.9 1313.01  4876.8 1308.99
  4883.2 1309.76  4891.3 1307.99  4897.6 1308.52  4912.1 1305.33  4947.4 1302.78
  4955.5 1300.62  4961.9 1301.38  4968.9 1298.96  4996.9 1300.28  4997.9 1298.84
  4998.4 1298.34    5013 1298.84  5015.5 1303.24  5025.6 1306.44  5035.7 1307.31
  5116.1 1310.22  5149.8 1309.47  5240.9 1311.57  5332.1 1315.25  5377.7 1319.88
#Mann= 3 ,-1 , 0
  4334.9     .05       0  4997.9     .03       0    5013     .05       0
Bank Sta=4997.9,5013
XS Rating Curve= 0 ,0
Exp/Cntr=0.3,0.1

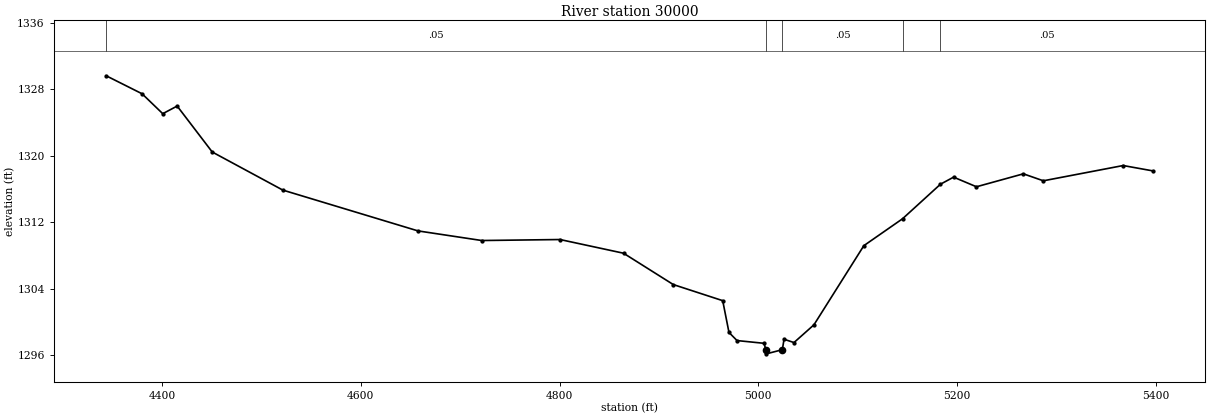
Type RM Length L Ch R = 1 ,30000   ,500,500,500
BEGIN DESCRIPTION:
BABYHEAD CREEK 60.0
END DESCRIPTION:
XS GIS Cut Line= 3
      2814505.66     10289653.14      2814101.48     10290169.96
      2813705.67     10290203.11
#Sta/Elev= 30
  4343.9 1329.65    4380 1327.48  4400.8 1325.08  4415.3    1326  4450.6 1320.46
  4521.6 1315.87  4657.6 1310.95  4721.8 1309.79  4800.5 1309.91  4864.4 1308.26
  4914.5 1304.48  4964.2 1302.54  4970.5 1298.71  4978.6 1297.73  5005.8  1297.4
  5007.6 1296.63  5008.1 1296.13  5024.2 1296.63  5025.9 1297.89  5035.9 1297.49
    5056 1299.63  5106.2 1309.17  5145.1 1312.41  5183.3 1316.58  5196.5 1317.43
  5219.5 1316.27  5266.7 1317.83  5286.8 1316.99  5367.1 1318.83  5397.2 1318.18
#Mann= 5 ,-1 , 0
  4343.9     .05       0  5007.6     .05       0  5024.2     .05       0
  5145.1     .12       0  5183.3     .05       0
Bank Sta=5007.6,5024.2
XS Rating Curve= 0 ,0
Exp/Cntr=0.3,0.1