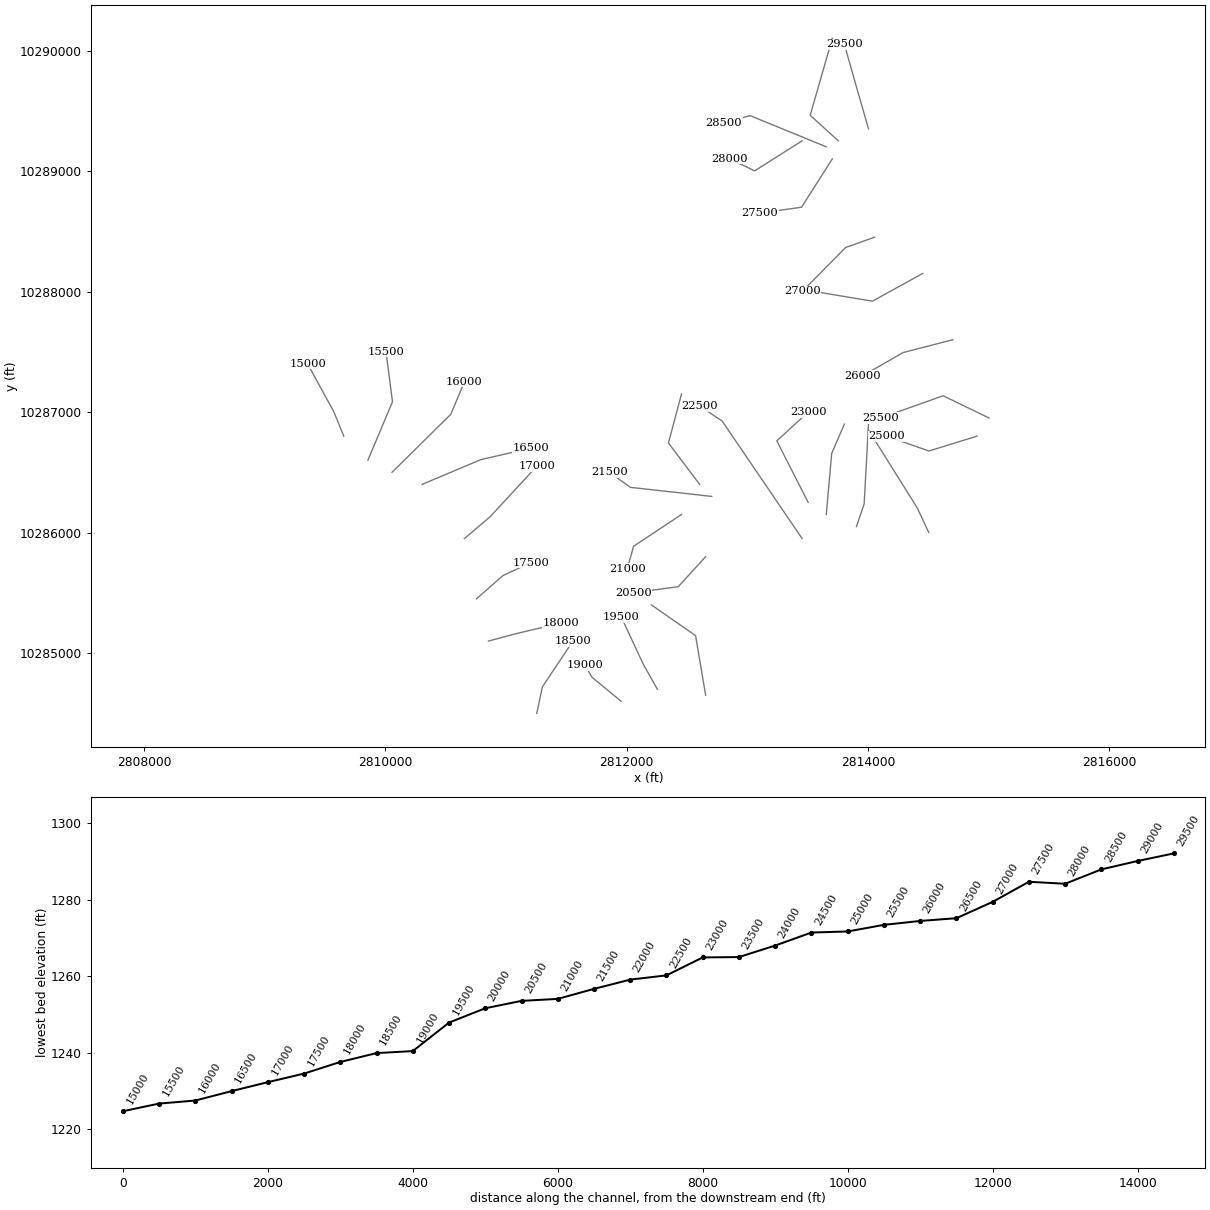
HEC-RAS study BABYHEAD CREEK.prj: BABYHEAD CREEK Base Level Engineering

--- BABYHEAD CREEK.g01 (geometry) --- (continued)

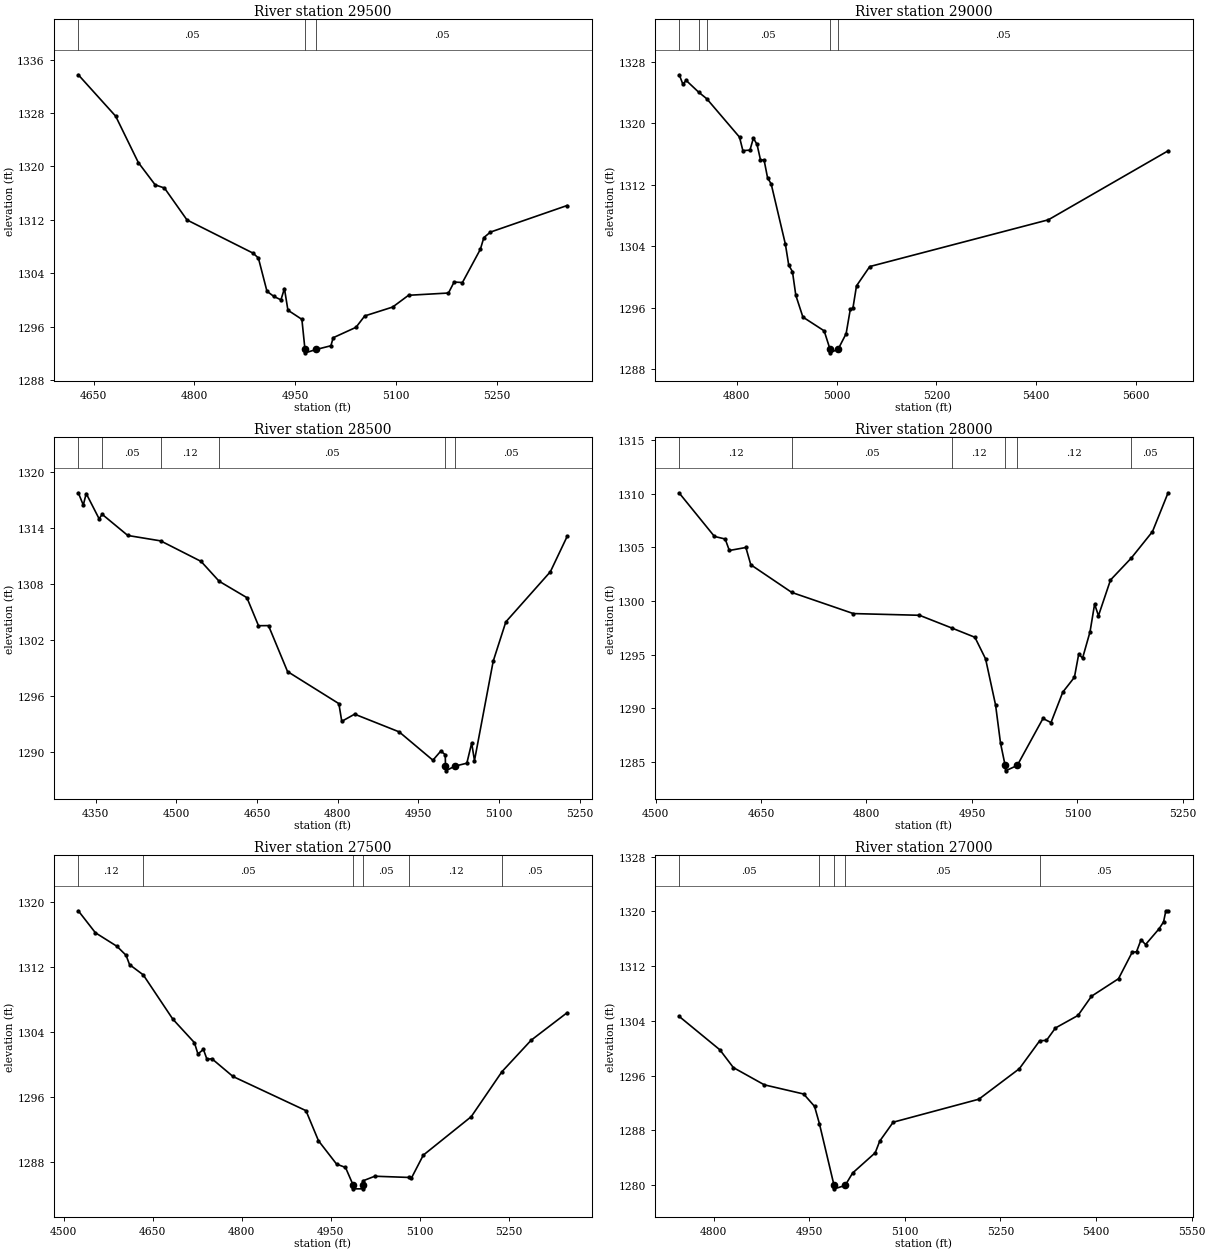
Type RM Length L Ch R = 1 ,29500   ,500,500,500
BEGIN DESCRIPTION:
BABYHEAD CREEK 59.0
END DESCRIPTION:
XS GIS Cut Line= 3
      2814005.68     10289353.11      2813902.46     10289711.44
      2813805.69      10290053.1
#Sta/Elev= 30
  4627.1 1333.72  4682.8 1327.52  4716.5 1320.59  4741.6 1317.25  4755.4 1316.78
    4789    1312  4887.3 1307.04  4895.3 1306.31  4908.1 1301.33  4918.5 1300.55
  4928.9 1300.05  4934.1 1301.74  4939.3  1298.5  4960.1 1297.13  4964.7 1292.62
  4965.2 1292.12  4981.3 1292.62  5003.3 1293.18  5006.7 1294.38  5040.7 1295.94
  5053.7 1297.64  5095.3 1298.97  5118.9 1300.73  5178.4 1301.07  5186.8 1302.71
  5199.2 1302.64  5225.9 1307.61  5231.1 1309.36  5240.8 1310.18  5355.1 1314.16
#Mann= 3 ,-1 , 0
  4627.1     .05       0  4964.7     .05       0  4981.3     .05       0
Bank Sta=4964.7,4981.3
XS Rating Curve= 0 ,0
Exp/Cntr=0.3,0.1

Type RM Length L Ch R = 1 ,29000   ,500,500,500
BEGIN DESCRIPTION:
BABYHEAD CREEK 58.0
END DESCRIPTION:
XS GIS Cut Line= 3
      2813755.71     10289253.09      2813522.19     10289464.65
      2813705.68      10290103.1
#Sta/Elev= 30
  4684.9  1326.3    4692 1325.09  4698.8 1325.56  4723.7 1324.04    4740 1323.18
  4805.6 1318.19  4812.3 1316.44  4826.5  1316.5  4833.4 1318.06  4840.7 1317.24
  4847.5 1315.27  4854.9 1315.19  4861.7 1312.93  4869.1 1312.09  4897.5 1304.27
  4904.2 1301.55  4911.7 1300.69  4918.4 1297.62  4932.6 1294.79  4975.2    1293
  4986.8 1290.64  4987.3 1290.14  5003.4 1290.64  5019.2 1292.63  5027.6 1295.81
  5032.8 1295.94    5040 1298.85  5066.5 1301.36  5424.4 1307.44  5664.3 1316.41
#Mann= 5 ,-1 , 0
  4684.9     .05       0  4723.7     .12       0    4740     .05       0
  4986.8     .03       0  5003.4     .05       0
Bank Sta=4986.8,5003.4
XS Rating Curve= 0 ,0
Exp/Cntr=0.3,0.1

Type RM Length L Ch R = 1 ,28500   ,500,500,500
BEGIN DESCRIPTION:
BABYHEAD CREEK 57.0
END DESCRIPTION:
XS GIS Cut Line= 3
      2813655.66     10289203.12      2813024.41     10289461.83
      2812805.66      10289403.1
#Sta/Elev= 30
  4317.8 1317.77  4327.1 1316.45  4332.5 1317.69  4356.5 1314.98  4362.2 1315.46
  4409.8 1313.19  4470.9 1312.61    4546 1310.41  4579.6 1308.28  4631.2 1306.52
  4652.8 1303.51  4671.4 1303.52  4706.8 1298.59  4802.2 1295.15  4807.6 1293.25
  4831.5 1294.02  4914.3 1292.12    4977 1289.08  4991.7 1290.06    5000 1289.67
  5000.4 1288.44  5000.9 1287.94  5017.6 1288.44  5040.1 1288.76  5049.1 1290.92
  5054.3 1289.04  5089.1  1299.7  5112.6 1303.92  5195.4  1309.3  5226.5 1313.08
#Mann= 6 ,-1 , 0
  4317.8     .12       0  4362.2     .05       0  4470.9     .12       0
  4579.6     .05       0  5000.4     .03       0  5017.6     .05       0
Bank Sta=5000.4,5017.6
XS Rating Curve= 0 ,0
Exp/Cntr=0.3,0.1

Type RM Length L Ch R = 1 ,28000   ,500,500,500
BEGIN DESCRIPTION:
BABYHEAD CREEK 56.0
END DESCRIPTION:
XS GIS Cut Line= 3
      2813455.69     10289253.12      2813061.86     10289003.65
      2812855.69     10289103.11
#Sta/Elev= 30
  4533.8 1310.07  4583.8 1306.03  4599.1 1305.79    4605 1304.72  4628.5    1305
  4635.5 1303.39  4693.8 1300.81  4781.3 1298.84  4875.4 1298.68  4921.5 1297.49
  4954.2 1296.63  4969.4 1294.61  4983.6 1290.31  4990.6 1286.77  4997.2 1284.68
  4997.7 1284.18  5014.4 1284.68    5051 1289.06  5062.4 1288.68  5079.2 1291.52
  5095.7  1292.9  5101.8 1295.06  5107.3 1294.69  5117.9 1297.14  5124.4 1299.72
  5129.9 1298.64    5147 1301.97  5176.5 1304.01  5206.7 1306.48  5228.9  1310.1
#Mann= 6 ,-1 , 0
  4533.8     .12       0  4693.8     .05       0  4921.5     .12       0
  4997.2     .07       0  5014.4     .12       0  5176.5     .05       0
Bank Sta=4997.2,5014.4
XS Rating Curve= 0 ,0
Exp/Cntr=0.3,0.1

Type RM Length L Ch R = 1 ,27500   ,500,500,500
BEGIN DESCRIPTION:
BABYHEAD CREEK 55.0
END DESCRIPTION:
XS GIS Cut Line= 3
       2813705.7     10289103.14      2813450.88     10288702.17
      2813105.65     10288653.11
#Sta/Elev= 30
  4524.9 1318.88  4553.7 1316.18  4590.1 1314.51  4605.4 1313.41  4611.3 1312.26
  4634.4    1311  4684.2 1305.56  4720.6 1302.67  4726.5 1301.28  4735.8 1301.84
  4741.7 1300.63  4750.1 1300.69  4785.6 1298.51  4908.6 1294.31  4929.7 1290.61
  4960.2 1287.74  4975.2 1287.33  4987.9  1285.2  4988.4  1284.7  5004.6  1284.7
  5005.1  1285.2  5005.2  1285.7  5024.6 1286.25  5082.5  1286.1  5086.1 1285.99
  5106.3 1288.84  5187.1 1293.57    5239 1299.11  5288.1 1302.97  5348.7 1306.35
#Mann= 6 ,-1 , 0
  4524.9     .12       0  4634.4     .05       0  4987.9     .05       0
  5005.1     .05       0  5082.5     .12       0    5239     .05       0
Bank Sta=4987.9,5005.1
XS Rating Curve= 0 ,0
Exp/Cntr=0.3,0.1

Type RM Length L Ch R = 1 ,27000   ,500,500,500
BEGIN DESCRIPTION:
BABYHEAD CREEK 54.0
END DESCRIPTION:
XS GIS Cut Line= 3
       2814055.7     10288453.12      2813816.27       10288368.
      2813455.68     10288003.11
#Sta/Elev= 30
  4745.9 1304.63  4809.6 1299.76  4830.8 1297.16  4879.4 1294.64  4941.1  1293.3
  4958.2 1291.49  4965.8 1288.97  4988.8 1279.94  4989.3 1279.44  5006.2 1279.94
    5018 1281.76  5053.4 1284.71  5060.5 1286.42  5081.6 1289.18    5216 1292.54
  5279.6    1297  5311.6 1301.09  5322.1 1301.13  5336.2 1302.95  5371.6 1304.78
  5392.8 1307.59  5435.2 1310.15  5456.5 1313.99  5463.5  1314.1  5470.6 1315.86
  5477.6 1315.14  5498.9 1317.45  5505.9 1318.46  5509.5 1320.08    5513 1320.08
#Mann= 5 ,-1 , 0
  4745.9     .05       0  4965.8     .05       0  4988.8     .05       0
  5006.2     .05       0  5311.6     .05       0
Bank Sta=4988.8,5006.2
XS Rating Curve= 0 ,0
Exp/Cntr=0.3,0.1

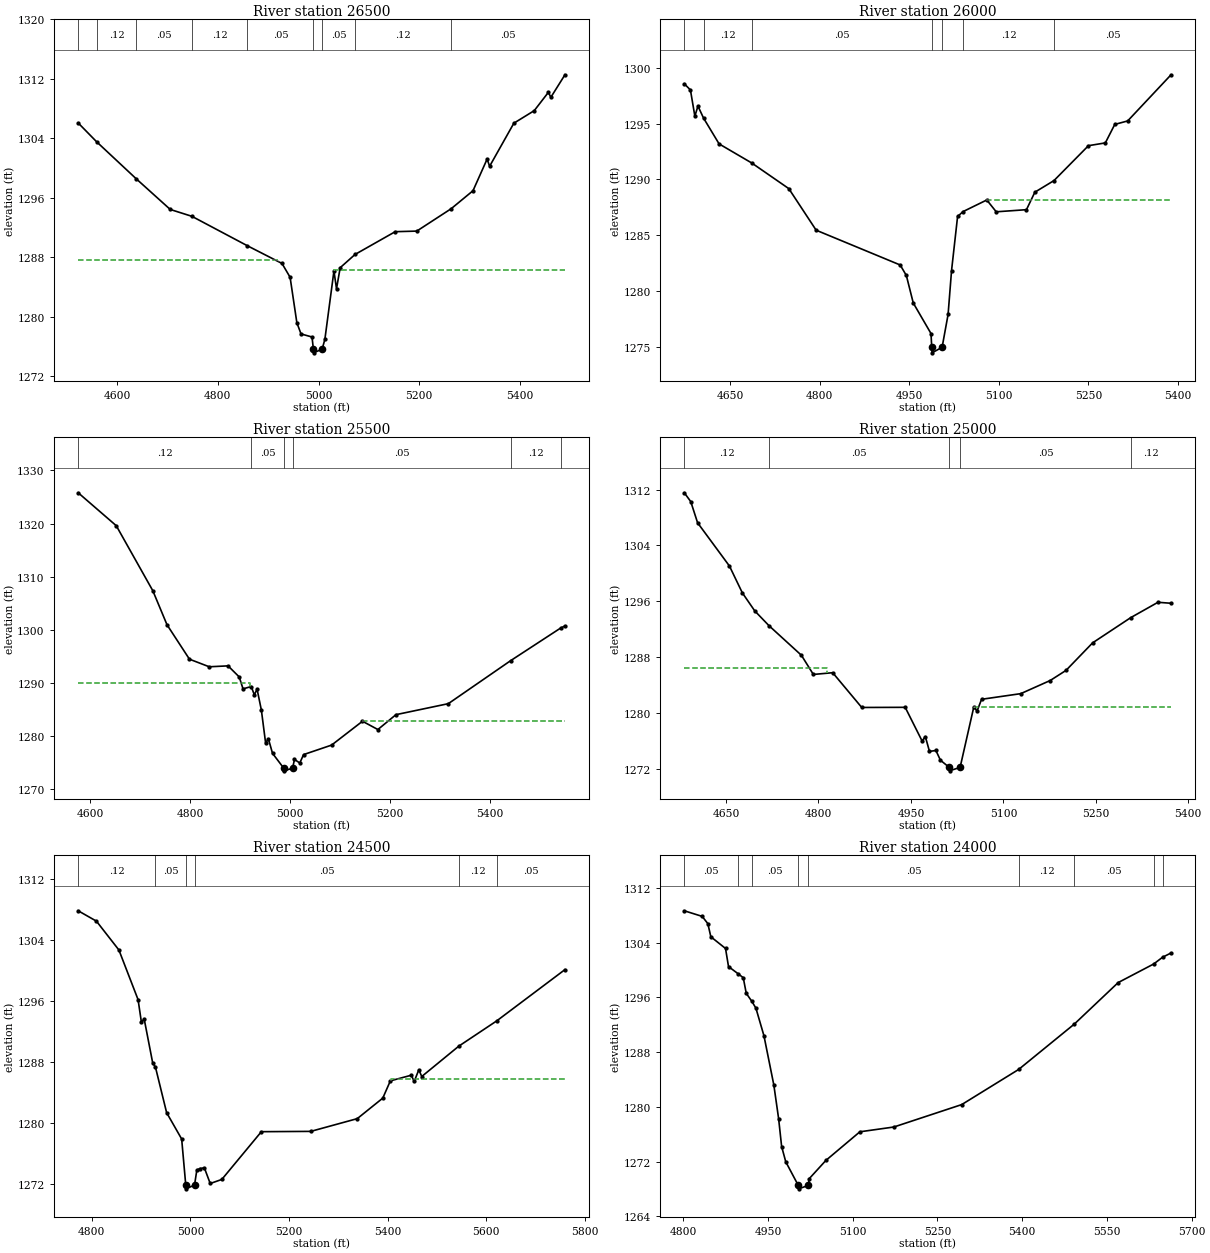
Type RM Length L Ch R = 1 ,26500   ,500,500,500
BEGIN DESCRIPTION:
BABYHEAD CREEK 53.0
END DESCRIPTION:
XS GIS Cut Line= 3
      2814455.68     10288153.11      2814038.07      10287922.6
      2813555.64     10288003.12
#Sta/Elev= 30
    4523 1306.08  4559.6 1303.55  4638.4 1298.56  4705.7 1294.45  4748.6 1293.53
  4858.8 1289.57  4927.5 1287.19  4943.6 1285.33    4957 1279.22  4965.3 1277.71
  4987.1  1277.3  4989.8 1275.67  4990.3 1275.17  5007.2 1275.67  5012.6 1276.98
  5030.6 1286.18  5035.7 1283.78    5043 1286.62  5072.5  1288.4  5152.2 1291.46
    5195 1291.54  5263.3 1294.55  5306.6 1296.97  5334.6 1301.22  5339.6 1300.26
  5387.7 1306.05  5428.2 1307.74  5456.1 1310.19  5461.2 1309.54  5489.1 1312.56
#Mann= 9 ,-1 , 0
    4523     .05       0  4559.6     .12       0  4638.4     .05       0
  4748.6     .12       0  4858.8     .05       0  4989.8     .05       0
  5007.2     .05       0  5072.5     .12       0  5263.3     .05       0
#XS Ineff= 2 , 0
         4922.27 1287.67 5030.68         1286.29
Permanent Ineff=
       F       F
Bank Sta=4989.8,5007.2
XS Rating Curve= 0 ,0
Exp/Cntr=0.3,0.1

Type RM Length L Ch R = 1 ,26000   ,500,500,500
BEGIN DESCRIPTION:
BABYHEAD CREEK 52.0
END DESCRIPTION:
XS GIS Cut Line= 3
      2814705.64      10287603.1      2814292.53     10287496.28
      2813955.69     10287303.11
#Sta/Elev= 30
  4573.3 1298.58  4583.6 1298.03    4591 1295.68  4596.2 1296.58  4605.5 1295.51
  4631.6 1293.19  4686.2 1291.48  4748.3 1289.18  4794.1 1285.45  4934.8 1282.33
  4945.1 1281.39  4956.7 1278.92  4986.4 1276.18  4987.6 1274.95  4988.1 1274.45
    5005 1274.95    5015 1277.89  5020.8 1281.83  5030.9 1286.68  5040.1 1287.12
  5079.8 1288.16  5095.6  1287.1  5146.2 1287.29  5160.3 1288.86  5192.3  1289.9
    5250 1293.03  5278.3 1293.28  5294.1 1294.94  5315.7 1295.25  5388.3 1299.39
#Mann= 7 ,-1 , 0
  4573.3     .05       0  4605.5     .12       0  4686.2     .05       0
  4987.6     .05       0    5005     .05       0  5040.1     .12       0
  5192.3     .05       0
#XS Ineff= 2 , 0
                         5078.98         1288.18
Permanent Ineff=
       F       F
Bank Sta=4987.6,5005
XS Rating Curve= 0 ,0
Exp/Cntr=0.3,0.1

Type RM Length L Ch R = 1 ,25500   ,500,500,500
BEGIN DESCRIPTION:
BABYHEAD CREEK 51.0
END DESCRIPTION:
XS GIS Cut Line= 3
      2815005.64     10286953.13      2814624.33     10287138.08
      2814105.73     10286953.13
#Sta/Elev= 30
  4576.2  1325.8  4652.4  1319.6  4725.6 1307.35    4754 1300.94  4798.9 1294.46
  4838.5 1293.03  4876.2  1293.2  4898.5 1291.12  4906.2 1288.87  4922.6 1289.31
  4928.8 1287.74  4934.3 1288.81  4942.9 1284.87  4951.4 1278.65  4956.9 1279.48
  4965.2 1276.73  4987.7 1273.93  4988.2 1273.43  5005.3 1273.93  5009.2 1275.57
  5019.8 1274.91  5027.4 1276.49  5083.5 1278.28  5145.3 1282.77  5176.1 1281.21
  5212.3 1284.01  5317.1 1286.08  5441.7 1294.17  5541.9 1300.32  5550.6 1300.72
#Mann= 6 ,-1 , 0
  4576.2     .12       0  4922.6     .05       0  4987.7     .05       0
  5005.3     .05       0  5441.7     .12       0  5541.9     .05       0
#XS Ineff= 2 , 0
         4920.91 1289.93 5145.23         1282.86
Permanent Ineff=
       F       F
Bank Sta=4987.7,5005.3
XS Rating Curve= 0 ,0
Exp/Cntr=0.3,0.1

Type RM Length L Ch R = 1 ,25000   ,500,500,500
BEGIN DESCRIPTION:
BABYHEAD CREEK 50.0
END DESCRIPTION:
XS GIS Cut Line= 3
      2814905.72     10286803.12      2814506.64     10286679.81
      2814155.67     10286803.12
#Sta/Elev= 30
  4582.3 1311.54  4592.8 1310.28  4603.9 1307.24  4655.6 1301.04  4676.5  1297.2
  4696.6 1294.62  4719.7  1292.5  4772.3 1288.26  4791.7 1285.51  4823.1 1285.76
  4870.2 1280.78  4940.7  1280.8  4968.1 1275.98  4973.4 1276.61  4980.1 1274.48
  4990.5 1274.62  4997.9 1273.22  5012.1  1272.2  5012.6  1271.7  5029.8  1272.2
    5052 1280.85  5057.3 1280.26  5064.6 1281.95  5128.2 1282.76  5175.9 1284.64
  5201.6 1286.09  5244.8 1290.04  5306.6 1293.65  5350.8 1295.85    5372 1295.71
#Mann= 5 ,-1 , 0
  4582.3     .12       0  4719.7     .05       0  5012.1     .05       0
  5029.8     .05       0  5306.6     .12       0
#XS Ineff= 2 , 0
         4813.07 1286.37 5052.84         1280.89
Permanent Ineff=
       F       F
Bank Sta=5012.1,5029.8
XS Rating Curve= 0 ,0
Exp/Cntr=0.3,0.1

Type RM Length L Ch R = 1 ,24500   ,500,500,500
BEGIN DESCRIPTION:
BABYHEAD CREEK 49.0
END DESCRIPTION:
XS GIS Cut Line= 3
      2814505.69      10286003.1      2814408.95     10286209.23
      2814005.71     10286853.08
#Sta/Elev= 30
  4772.3 1307.86  4809.3  1306.5  4854.9 1302.72  4893.8 1296.21  4900.6 1293.22
  4906.1  1293.7  4923.4 1287.93  4929.1 1287.35  4951.7  1281.4  4982.2 1277.95
  4990.5 1271.92    4991 1271.42  5008.3 1271.92    5013 1273.89  5018.9 1274.06
  5028.2 1274.18  5040.1 1272.12  5063.6 1272.65  5143.9 1278.91  5244.1 1278.95
  5338.4 1280.62  5390.2 1283.31  5405.5 1285.57    5448 1286.31  5453.9 1285.49
  5463.3 1287.03  5469.2 1286.14  5544.4 1290.12  5621.3 1293.43  5759.7 1300.15
#Mann= 6 ,-1 , 0
  4772.3     .12       0  4929.1     .05       0  4990.5     .05       0
  5008.3     .05       0  5544.4     .12       0  5621.3     .05       0
#XS Ineff= 2 , 0
                         5405.91         1285.76
Permanent Ineff=
       F       F
Bank Sta=4990.5,5008.3
XS Rating Curve= 0 ,0
Exp/Cntr=0.3,0.1

Type RM Length L Ch R = 1 ,24000   ,500,500,500
BEGIN DESCRIPTION:
BABYHEAD CREEK 48.0
END DESCRIPTION:
XS GIS Cut Line= 3
      2813905.68      10286053.1      2813969.68     10286240.58
      2814005.68      10286903.1
#Sta/Elev= 30
  4801.9 1308.68  4833.6 1307.86  4843.6  1306.8  4848.9 1304.88  4874.9 1303.17
  4880.2 1300.52  4897.7 1299.44  4906.3 1298.89  4911.6 1296.61  4921.3 1295.46
  4928.7 1294.44  4942.9 1290.41  4960.4 1283.21  4968.9 1278.28  4974.2 1274.21
  4981.5 1271.98  5003.7 1268.52  5004.2 1268.02  5021.5 1268.52  5023.1 1269.51
  5052.6 1272.18  5112.7 1276.36  5172.8 1277.06    5293 1280.34  5393.8 1285.48
  5492.4 1292.12  5569.9 1298.18  5632.8  1300.9  5648.4 1301.88  5663.5 1302.51
#Mann= 9 ,-1 , 0
  4801.9     .05       0  4897.7     .12       0  4921.3     .05       0
  5003.7     .05       0  5021.5     .05       0  5393.8     .12       0
  5492.4     .05       0  5632.8     .12       0  5648.4     .05       0
Bank Sta=5003.7,5021.5
XS Rating Curve= 0 ,0
Exp/Cntr=0.3,0.1

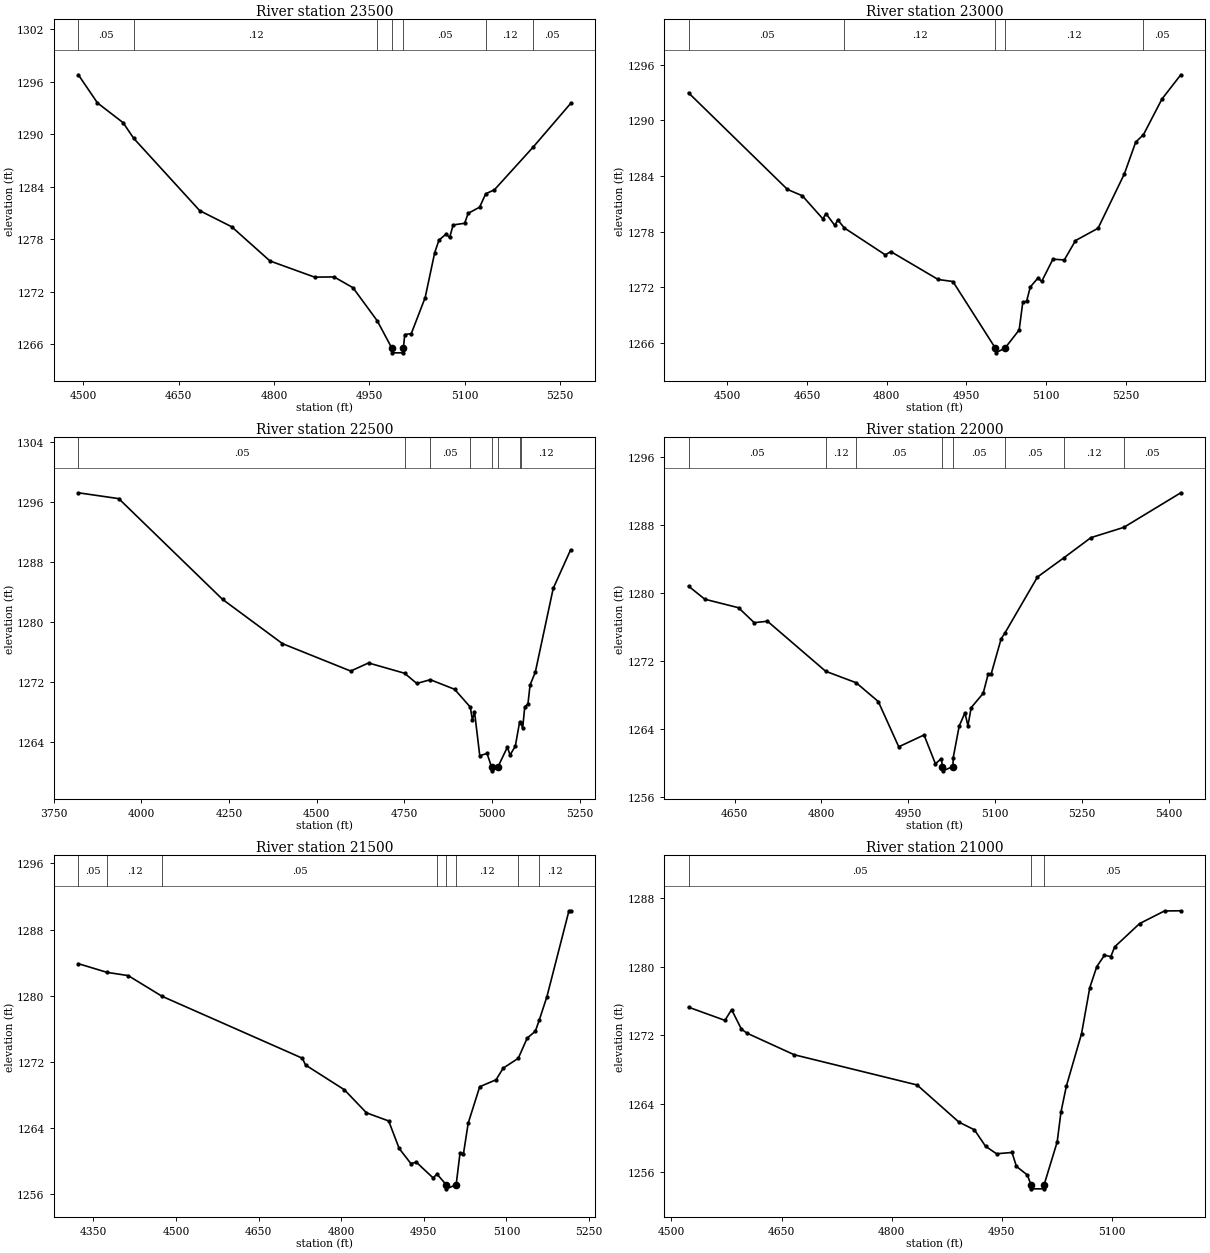
Type RM Length L Ch R = 1 ,23500   ,500,500,500
BEGIN DESCRIPTION:
BABYHEAD CREEK 47.0
END DESCRIPTION:
XS GIS Cut Line= 3
      2813655.68     10286153.08       2813700.4     10286658.61
      2813805.68      10286903.1
#Sta/Elev= 30
  4492.5 1296.78  4522.6 1293.56  4562.8 1291.31  4579.6 1289.51  4683.3 1281.25
  4733.5 1279.41  4793.7  1275.5    4864 1273.65  4894.4 1273.68  4924.2 1272.44
  4962.4 1268.65  4985.5  1265.5    4986    1265  5002.9    1265  5003.4  1265.5
  5005.5 1267.09  5015.8  1267.2  5037.6 1271.31  5052.6 1276.45  5059.3 1277.88
  5070.2 1278.56  5076.1 1278.19  5081.6 1279.62  5099.7 1279.81  5105.1 1280.94
  5123.2 1281.65  5132.8 1283.18  5146.4 1283.63  5207.4 1288.52  5266.2  1293.5
#Mann= 7 ,-1 , 0
  4492.5     .05       0  4579.6     .12       0  4962.4     .05       0
  4985.5     .05       0  5003.4     .05       0  5132.8     .12       0
  5207.4     .05       0
Bank Sta=4985.5,5003.4
XS Rating Curve= 0 ,0
Exp/Cntr=0.3,0.1

Type RM Length L Ch R = 1 ,23000   ,500,500,500
BEGIN DESCRIPTION:
BABYHEAD CREEK 46.0
END DESCRIPTION:
XS GIS Cut Line= 3
      2813505.68     10286253.12      2813245.66      10286763.5
      2813505.69     10287003.12
#Sta/Elev= 30
  4427.2 1292.98  4613.4 1282.55  4641.3 1281.87  4680.1 1279.37  4685.7 1279.95
  4702.4 1278.67    4708 1279.26  4720.5 1278.39  4797.5 1275.49  4807.9 1275.84
  4896.9 1272.83  4924.7 1272.61  5004.7 1265.41  5005.2 1264.91  5022.6 1265.41
  5049.4 1267.38  5056.2 1270.36  5063.5 1270.49  5070.3 1272.02  5084.5 1272.97
  5091.9 1272.63  5112.9 1275.02  5134.4 1274.94  5155.4 1277.03  5197.9 1278.36
  5247.3 1284.22  5268.8 1287.67  5283.3 1288.46  5318.1 1292.31  5353.6 1294.93
#Mann= 5 ,-1 , 0
  4427.2     .05       0  4720.5     .12       0  5004.7     .07       0
  5022.6     .12       0  5283.3     .05       0
Bank Sta=5004.7,5022.6
XS Rating Curve= 0 ,0
Exp/Cntr=0.3,0.1

Type RM Length L Ch R = 1 ,22500   ,500,500,500
BEGIN DESCRIPTION:
BABYHEAD CREEK 45.0
END DESCRIPTION:
XS GIS Cut Line= 3
       2813455.7     10285953.09      2812791.92     10286928.81
      2812605.69     10287053.11
#Sta/Elev= 30
  3819.9 1297.22  3935.2 1296.44  4231.1 1283.04  4402.1 1277.14  4596.7 1273.49
  4647.5 1274.57  4750.3  1273.2  4785.2 1271.84  4823.7 1272.34  4892.9 1271.07
  4937.9 1268.69  4943.8 1266.97  4949.8  1268.1  4964.8 1262.23  4985.7 1262.52
  4998.5 1260.71    4999 1260.21  5016.5 1260.71  5043.6 1263.37  5051.2 1262.32
  5066.2 1263.49  5078.6 1266.74  5081.8 1266.59  5087.2 1265.91  5093.2 1268.75
  5102.2 1269.09  5108.3 1271.64  5123.3 1273.35  5174.3 1284.49  5223.9 1289.62
#Mann= 8 ,-1 , 0
  3819.9     .05       0  4750.3     .12       0  4823.7     .05       0
  4937.9     .12       0  4998.5     .07       0  5016.5     .12       0
  5078.6     .05       0  5081.8     .12       0
Bank Sta=4998.5,5016.5
XS Rating Curve= 0 ,0
Exp/Cntr=0.3,0.1

Type RM Length L Ch R = 1 ,22000   ,500,500,500
BEGIN DESCRIPTION:
BABYHEAD CREEK 44.0
END DESCRIPTION:
XS GIS Cut Line= 3
      2812605.69      10286403.1       2812347.1     10286746.28
      2812455.69     10287153.14
#Sta/Elev= 30
  4570.3 1280.84  4598.4  1279.3  4656.7  1278.3  4683.8 1276.54  4706.7 1276.71
  4807.3 1270.82    4860 1269.47  4898.2 1267.26  4933.6 1261.93  4977.3 1263.32
    4997 1259.93  5007.1 1260.54  5009.2  1259.6  5009.7  1259.1  5027.2  1259.6
  5027.8 1260.67  5038.1 1264.38    5048 1265.92  5053.2 1264.41  5058.8 1266.54
  5079.5 1268.22  5088.1 1270.47  5093.3 1270.49  5110.6 1274.65  5116.9  1275.3
  5173.4 1281.92  5219.7 1284.21  5265.8 1286.55  5322.6 1287.76  5421.1 1291.83
#Mann= 8 ,-1 , 0
  4570.3     .05       0  4807.3     .12       0    4860     .05       0
  5009.2     .05       0  5027.2     .05       0  5116.9     .05       0
  5219.7     .12       0  5322.6     .05       0
Bank Sta=5009.2,5027.2
XS Rating Curve= 0 ,0
Exp/Cntr=0.3,0.1

Type RM Length L Ch R = 1 ,21500   ,500,500,500
BEGIN DESCRIPTION:
BABYHEAD CREEK 43.0
END DESCRIPTION:
XS GIS Cut Line= 3
      2812705.67     10286303.11      2812032.65     10286378.18
       2811855.7      10286503.1
#Sta/Elev= 30
  4322.8 1283.88  4374.9 1282.83  4413.3 1282.44  4474.8 1279.94  4729.5 1272.46
  4735.3 1271.64  4805.8 1268.65    4846 1265.86  4886.3 1264.88  4905.3 1261.56
  4926.5 1259.74  4936.6 1259.89  4966.8 1258.01  4974.2 1258.45  4990.7 1257.18
  4991.2 1256.68  5008.8 1257.18  5015.9 1261.04  5022.1 1260.93  5030.7 1264.62
  5051.6 1269.02  5081.2 1269.85  5094.2 1271.26  5121.6 1272.45  5137.8 1274.89
  5152.6 1275.72    5160 1277.13  5173.5 1279.87  5213.6 1290.27  5216.6 1290.27
#Mann= 8 ,-1 , 0
  4322.8     .05       0  4374.9     .12       0  4474.8     .05       0
  4974.2     .12       0  4990.7     .07       0  5008.8     .12       0
  5121.6     .05       0    5160     .12       0
Bank Sta=4990.7,5008.8
XS Rating Curve= 0 ,0
Exp/Cntr=0.3,0.1

Type RM Length L Ch R = 1 ,21000   ,500,500,500
BEGIN DESCRIPTION:
BABYHEAD CREEK 42.0
END DESCRIPTION:
XS GIS Cut Line= 3
      2812455.67      10286153.1      2812058.47     10285889.53
      2812005.67     10285703.06
#Sta/Elev= 30
  4523.3 1275.29  4572.9 1273.75  4581.9 1275.01  4595.3 1272.73    4603 1272.25
  4667.3 1269.73  4834.6  1266.2  4891.7 1261.85  4912.7 1260.96  4927.8 1259.04
  4942.8 1258.16  4963.9 1258.31  4969.9 1256.68  4984.9 1255.67  4989.6 1254.56
  4990.1 1254.06  5007.2 1254.06  5007.7 1254.56  5025.4 1259.54  5030.6 1263.04
  5037.9 1266.06  5058.6 1272.19  5069.8 1277.57  5079.4 1280.04  5089.8 1281.36
  5098.5 1281.21  5103.7 1282.34  5137.6 1285.06  5171.6 1286.54  5193.8 1286.56
#Mann= 3 ,-1 , 0
  4523.3     .05       0  4989.6     .03       0  5007.7     .05       0
Bank Sta=4989.6,5007.7
XS Rating Curve= 0 ,0
Exp/Cntr=0.3,0.1

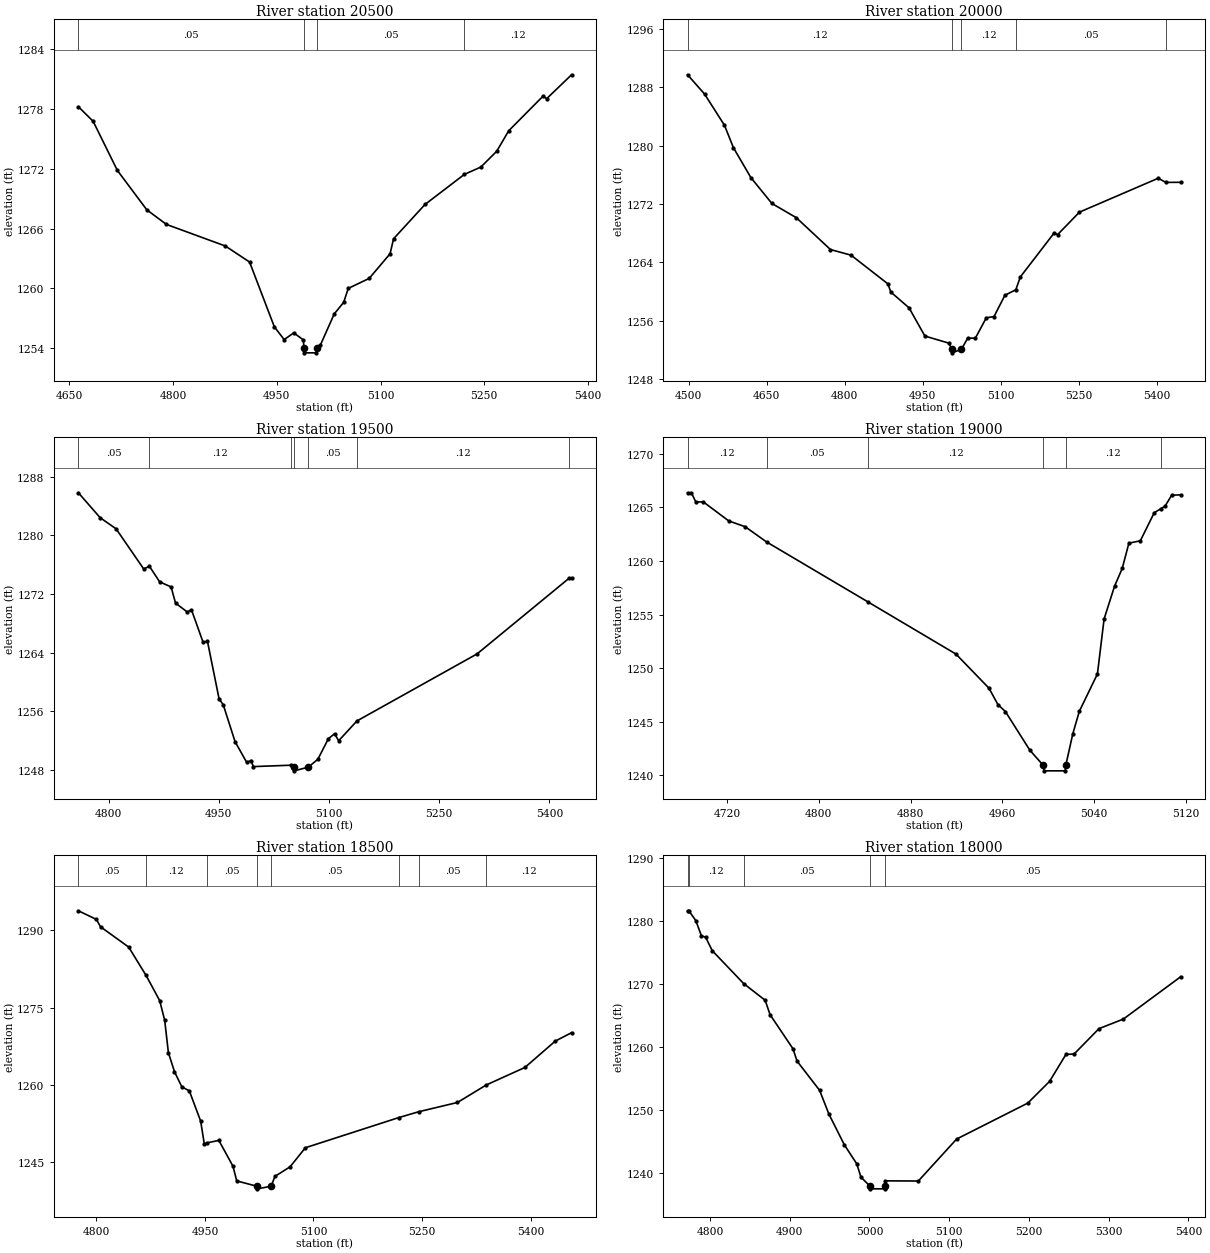
Type RM Length L Ch R = 1 ,20500   ,500,500,500
BEGIN DESCRIPTION:
BABYHEAD CREEK 41.0
END DESCRIPTION:
XS GIS Cut Line= 3
       2812655.7     10285803.12      2812428.47     10285554.25
      2812055.66     10285503.11
#Sta/Elev= 30
    4663 1278.21  4684.3 1276.75  4719.4 1271.82    4762 1267.87  4790.4 1266.41
  4875.5 1264.25  4910.6 1262.64  4946.4 1256.15  4960.6 1254.87  4974.5 1255.54
  4988.3 1254.84  4989.3 1254.04  4989.8 1253.54  5006.9 1253.54  5007.4 1254.04
  5012.9  1254.3  5033.1 1257.45  5046.7  1258.6  5053.3    1260  5083.6    1261
  5113.8 1263.47  5118.8 1264.97  5164.3 1268.41  5221.3 1271.43  5245.1 1272.16
  5268.1 1273.75  5285.4  1275.8  5335.2 1279.28  5340.2 1279.01  5376.3 1281.41
#Mann= 4 ,-1 , 0
    4663     .05       0  4989.3     .05       0  5007.4     .05       0
  5221.3     .12       0
Bank Sta=4989.3,5007.4
XS Rating Curve= 0 ,0
Exp/Cntr=0.3,0.1

Type RM Length L Ch R = 1 ,20000   ,500,500,500
BEGIN DESCRIPTION:
BABYHEAD CREEK 40.0
END DESCRIPTION:
XS GIS Cut Line= 3
      2812655.68     10284653.12      2812572.26     10285148.14
      2812205.71      10285403.1
#Sta/Elev= 30
    4498  1289.7  4530.8 1287.05    4569 1282.78  4586.2 1279.71  4619.7 1275.62
  4660.2 1272.07  4707.2 1270.12  4772.8 1265.76  4812.4 1264.99  4883.4 1261.05
  4888.8 1259.94  4923.9 1257.78  4954.4 1253.91    5000 1252.95  5006.7 1252.11
  5007.2 1251.61  5024.8 1252.11  5036.7 1253.62  5051.6 1253.63  5072.5 1256.41
  5087.4 1256.58  5108.3  1259.5  5129.3 1260.25    5138 1262.01  5202.9 1268.02
  5209.6  1267.8  5251.6 1270.88  5403.3 1275.53  5417.7 1274.96  5446.5 1274.97
#Mann= 5 ,-1 , 0
    4498     .12       0  5006.7     .07       0  5024.8     .12       0
  5129.3     .05       0  5417.7     .12       0
Bank Sta=5006.7,5024.8
XS Rating Curve= 0 ,0
Exp/Cntr=0.3,0.1

Type RM Length L Ch R = 1 ,19500   ,500,500,500
BEGIN DESCRIPTION:
BABYHEAD CREEK 39.0
END DESCRIPTION:
XS GIS Cut Line= 3
      2812255.68     10284703.11      2812137.39      10284913.2
      2811955.67     10285303.13
#Sta/Elev= 30
  4758.9 1285.83  4788.5 1282.43  4810.2 1280.91  4847.8 1275.43  4855.6 1275.79
  4869.5 1273.67  4885.1 1272.97  4891.1 1270.77  4907.1 1269.55  4912.8 1269.86
  4928.7  1265.4  4934.5 1265.59  4950.4 1257.69  4956.1 1256.88  4972.1 1251.86
    4988 1249.01  4993.7 1249.27  4997.1 1248.44  5048.5 1248.63  5052.2 1248.36
  5052.7 1247.86  5071.7 1248.36  5084.8 1249.43  5099.2 1252.25  5107.6 1252.92
  5113.2 1251.97    5138 1254.67  5301.6 1263.83  5427.3  1274.2  5430.2 1274.21
#Mann= 7 ,-1 , 0
  4758.9     .05       0  4855.6     .12       0  5048.5     .05       0
  5052.2     .07       0  5071.7     .05       0    5138     .12       0
  5427.3     .05       0
Bank Sta=5052.2,5071.7
XS Rating Curve= 0 ,0
Exp/Cntr=0.3,0.1

Type RM Length L Ch R = 1 ,19000   ,500,500,500
BEGIN DESCRIPTION:
BABYHEAD CREEK 38.0
END DESCRIPTION:
XS GIS Cut Line= 3
      2811955.71     10284603.09      2811713.26      10284803.1
      2811655.68     10284903.11
#Sta/Elev= 30
  4685.7 1266.37    4689 1266.37  4692.9 1265.51  4699.4 1265.52  4721.6 1263.74
  4735.9  1263.2  4754.5 1261.78    4843 1256.17  4919.6  1251.3  4948.3 1248.12
  4956.1 1246.59  4962.6 1245.94  4983.9 1242.33  4995.7  1240.9  4996.2  1240.4
  5014.7  1240.4  5015.2  1240.9  5021.3 1243.84    5027 1245.95  5042.8 1249.45
  5048.6 1254.58  5057.7 1257.64  5064.4  1259.3  5070.2 1261.66  5080.2 1261.89
  5092.3 1264.51  5097.9 1264.87  5101.7 1265.12  5107.5 1266.14  5115.4 1266.18
#Mann= 6 ,-1 , 0
  4685.7     .12       0  4754.5     .05       0    4843     .12       0
  4995.7     .07       0  5015.2     .12       0  5097.9     .05       0
Bank Sta=4995.7,5015.2
XS Rating Curve= 0 ,0
Exp/Cntr=0.3,0.1

Type RM Length L Ch R = 1 ,18500   ,500,500,500
BEGIN DESCRIPTION:
BABYHEAD CREEK 37.0
END DESCRIPTION:
XS GIS Cut Line= 3
      2811255.69     10284503.15      2811302.13     10284723.21
      2811555.66     10285103.07
#Sta/Elev= 30
  4775.1 1293.74  4799.9 1292.07  4805.7 1290.64  4844.6 1286.71  4868.6 1281.23
  4887.5 1276.33  4894.4  1272.5  4899.5 1266.25  4907.9 1262.57  4918.1 1259.62
  4928.4 1258.87  4944.1 1252.99  4949.2  1248.5  4952.6 1248.77  4969.2 1249.27
  4988.8 1244.24  4993.9 1241.42  5021.9 1240.38  5022.4 1239.88  5041.5 1240.38
  5046.7 1242.29  5067.7 1244.15  5088.8 1247.84  5217.6 1253.67  5245.6 1254.82
    5299 1256.61  5338.7 1259.99  5392.2 1263.39  5434.2  1268.5  5456.7 1270.13
#Mann= 8 ,-1 , 0
  4775.1     .05       0  4868.6     .12       0  4952.6     .05       0
  5021.9     .05       0  5041.5     .05       0  5217.6     .12       0
  5245.6     .05       0  5338.7     .12       0
Bank Sta=5021.9,5041.5
XS Rating Curve= 0 ,0
Exp/Cntr=0.3,0.1

Type RM Length L Ch R = 1 ,18000   ,500,500,500
BEGIN DESCRIPTION:
BABYHEAD CREEK 36.0
END DESCRIPTION:
XS GIS Cut Line= 3
      2810855.73     10285103.12      2811076.03     10285162.26
      2811455.71     10285253.12
#Sta/Elev= 30
  4771.9 1281.69  4773.5 1281.69  4782.2 1280.14  4789.3  1277.7  4794.4 1277.52
  4802.9 1275.35  4842.4 1270.12  4869.2 1267.49  4875.4 1265.19  4904.1 1259.79
  4909.2 1257.83  4937.5 1253.19  4949.2 1249.41  4968.6 1244.52  4984.1 1241.53
  4989.3 1239.42  5000.1 1238.06  5000.6 1237.56  5019.2 1237.56  5019.7 1238.06
  5020.1 1238.83  5061.3  1238.8  5109.3 1245.46  5198.6 1251.17  5225.9 1254.62
  5246.4 1258.89  5256.7 1258.96  5287.8 1262.98  5318.4  1264.5  5390.4 1271.23
#Mann= 5 ,-1 , 0
  4771.9     .05       0  4773.5     .12       0  4842.4     .05       0
  5000.1     .05       0  5019.7     .05       0
Bank Sta=5000.1,5019.7
XS Rating Curve= 0 ,0
Exp/Cntr=0.3,0.1

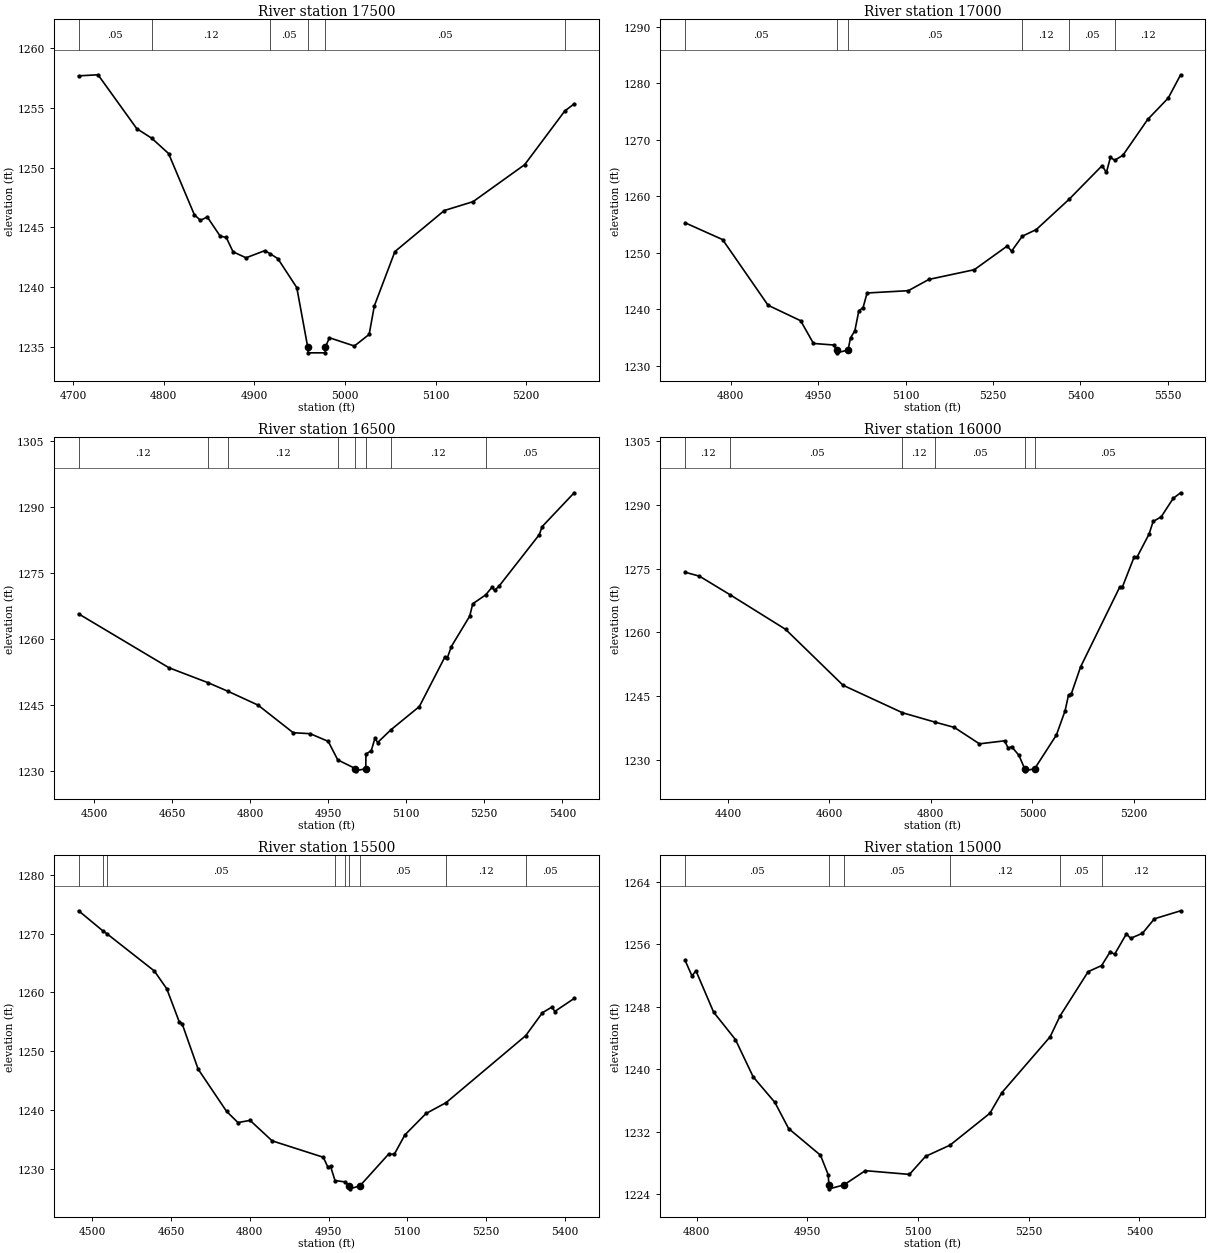
Type RM Length L Ch R = 1 ,17500   ,500,500,500
BEGIN DESCRIPTION:
BABYHEAD CREEK 35.0
END DESCRIPTION:
XS GIS Cut Line= 3
      2810755.67      10285453.1      2810976.25     10285647.02
      2811205.71     10285753.12
#Sta/Elev= 30
  4706.3 1257.66  4727.7 1257.75  4770.4 1253.25  4786.9 1252.45  4805.5 1251.17
  4833.9 1246.06  4840.6 1245.59  4848.2 1245.87  4862.4 1244.27  4869.1 1244.16
  4876.6 1242.96  4890.9 1242.46  4911.7 1243.06  4917.7 1242.79    4926 1242.39
  4946.9 1239.97  4958.9 1235.02  4959.4 1234.52    4978 1234.52  4978.5 1235.02
  4982.9 1235.78  5010.4 1235.09  5026.7 1236.06  5032.4 1238.44  5055.1 1242.98
  5109.6 1246.41  5141.3 1247.15  5198.2 1250.24  5242.5 1254.73  5252.8 1255.32
#Mann= 6 ,-1 , 0
  4706.3     .05       0  4786.9     .12       0  4917.7     .05       0
  4958.9     .05       0  4978.5     .05       0  5242.5     .12       0
Bank Sta=4958.9,4978.5
XS Rating Curve= 0 ,0
Exp/Cntr=0.3,0.1

Type RM Length L Ch R = 1 ,17000   ,500,500,500
BEGIN DESCRIPTION:
BABYHEAD CREEK 34.0
END DESCRIPTION:
XS GIS Cut Line= 3
      2810655.69     10285953.12      2810867.71     10286133.08
      2811255.69     10286553.11
#Sta/Elev= 30
  4721.9 1255.28  4786.2 1252.31  4864.2 1240.69  4920.1 1237.95  4942.1 1233.93
  4977.3 1233.65  4981.7 1232.77  4982.2 1232.27  5001.4 1232.77  5005.6 1234.93
    5013 1236.15  5019.8 1239.68  5027.2 1240.29    5034 1242.86  5104.8 1243.27
    5140 1245.26  5217.9 1246.98  5274.4 1251.17  5281.8 1250.26  5300.3 1252.91
  5324.3 1254.09  5380.4 1259.43  5437.1 1265.39  5444.5 1264.18  5451.3 1266.84
  5458.9 1266.35  5472.8 1267.23  5515.4 1273.58  5550.5 1277.35  5571.8 1281.47
#Mann= 6 ,-1 , 0
  4721.9     .05       0  4981.7     .03       0  5001.4     .05       0
  5300.3     .12       0  5380.4     .05       0  5458.9     .12       0
Bank Sta=4981.7,5001.4
XS Rating Curve= 0 ,0
Exp/Cntr=0.3,0.1

Type RM Length L Ch R = 1 ,16500   ,500,500,500
BEGIN DESCRIPTION:
BABYHEAD CREEK 33.0
END DESCRIPTION:
XS GIS Cut Line= 3
      2810305.72     10286403.13      2810793.66     10286608.76
      2811205.69     10286703.11
#Sta/Elev= 30
  4470.5 1265.67  4644.1  1253.4  4718.9 1250.01  4757.9 1248.02  4815.2  1244.9
  4882.8 1238.61  4915.4 1238.39  4950.1 1236.64  4968.4 1232.42  5002.5 1230.43
    5003 1229.93  5022.2 1230.43  5022.6 1233.72  5032.9 1234.56  5039.9 1237.36
  5045.1 1236.38  5070.3 1239.25  5125.2 1244.57  5173.8 1255.74    5179 1255.66
  5186.7 1258.24  5221.9 1265.14  5227.8 1267.96  5252.6 1269.99  5264.8 1271.73
  5269.9 1271.01  5279.1  1272.1  5355.7 1283.71  5361.1 1285.53  5422.7 1293.24
#Mann= 8 ,-1 , 0
  4470.5     .12       0  4718.9     .05       0  4757.9     .12       0
  4968.4     .05       0  5002.5     .03       0  5022.2     .05       0
  5070.3     .12       0  5252.6     .05       0
Bank Sta=5002.5,5022.2
XS Rating Curve= 0 ,0
Exp/Cntr=0.3,0.1

Type RM Length L Ch R = 1 ,16000   ,500,500,500
BEGIN DESCRIPTION:
BABYHEAD CREEK 32.0
END DESCRIPTION:
XS GIS Cut Line= 3
      2810055.66     10286503.09      2810542.56     10286983.77
      2810655.67     10287253.08
#Sta/Elev= 30
  4315.8 1274.17  4344.1 1273.24    4405 1268.83  4513.8 1260.74  4626.9  1247.6
  4744.1 1241.13    4808 1238.93  4846.2 1237.68  4895.7 1233.82  4945.2 1234.53
  4952.2 1232.85  4959.3 1233.14  4973.5 1231.12  4984.8 1227.97  4985.3 1227.47
  5004.5 1227.97  5047.4 1235.91  5064.4 1241.58  5071.2  1245.3  5076.6 1245.54
    5095 1251.91  5171.7 1270.58  5177.1 1270.63  5200.8 1277.84  5206.3 1277.75
    5230 1283.17  5237.9  1286.1  5253.8 1287.19  5277.5 1291.55  5292.1 1292.85
#Mann= 6 ,-1 , 0
  4315.8     .12       0    4405     .05       0  4744.1     .12       0
    4808     .05       0  4984.8     .03       0  5004.5     .05       0
Bank Sta=4984.8,5004.5
XS Rating Curve= 0 ,0
Exp/Cntr=0.3,0.1

Type RM Length L Ch R = 1 ,15500   ,500,500,500
BEGIN DESCRIPTION:
BABYHEAD CREEK 31.0
END DESCRIPTION:
XS GIS Cut Line= 3
      2809855.69     10286603.12      2810059.55     10287088.44
      2810005.68     10287503.16
#Sta/Elev= 30
  4473.6 1273.87  4519.4 1270.49  4528.3 1269.92  4617.8 1263.66  4641.6 1260.63
  4665.3 1255.04  4670.8 1254.71  4701.4 1246.99  4755.6 1239.82  4777.3 1237.92
  4800.4 1238.29  4842.4 1234.82    4940 1232.03  4948.4 1230.41  4953.8 1230.48
  4962.3 1228.08  4981.9 1227.84  4989.8 1227.17  4990.3 1226.67  5009.8 1227.17
  5064.5 1232.57  5075.3 1232.53  5095.5 1235.82  5135.8 1239.46  5174.1  1241.3
  5325.8 1252.67  5357.6 1256.56  5376.1 1257.55  5381.1 1256.77  5418.2 1258.99
#Mann= 9 ,-1 , 0
  4473.6     .05       0  4519.4     .12       0  4528.3     .05       0
  4962.3     .12       0  4981.9     .05       0  4989.8     .05       0
  5009.8     .05       0  5174.1     .12       0  5325.8     .05       0
Bank Sta=4989.8,5009.8
XS Rating Curve= 0 ,0
Exp/Cntr=0.3,0.1

Type RM Length L Ch R = 1 ,15000   ,500,500,500
BEGIN DESCRIPTION:
BABYHEAD CREEK 30.0
END DESCRIPTION:
XS GIS Cut Line= 3
      2809655.67     10286803.16      2809574.35     10287002.94
      2809355.69      10287403.1
#Sta/Elev= 30
  4784.3 1253.95  4793.6 1251.96    4799 1252.62    4823 1247.31  4852.5 1243.81
  4876.6 1239.02    4906 1235.75  4924.6  1232.4  4967.8 1228.98  4978.2  1226.5
  4979.3 1225.17  4979.8 1224.67  4999.5 1225.17  5028.6    1227  5088.4 1226.52
  5110.2 1228.83  5143.4 1230.27  5197.5 1234.36  5213.6 1236.99  5279.1 1244.16
  5292.6 1246.84  5330.7 1252.51  5348.9 1253.29  5360.7 1255.08  5366.4 1254.72
  5382.5 1257.35  5388.2 1256.78  5404.3 1257.43  5420.4 1259.28    5456 1260.31
#Mann= 6 ,-1 , 0
  4784.3     .05       0  4979.3     .03       0  4999.5     .05       0
  5143.4     .12       0  5292.6     .05       0  5348.9     .12       0
Bank Sta=4979.3,4999.5
XS Rating Curve= 0 ,0
Exp/Cntr=0.3,0.1