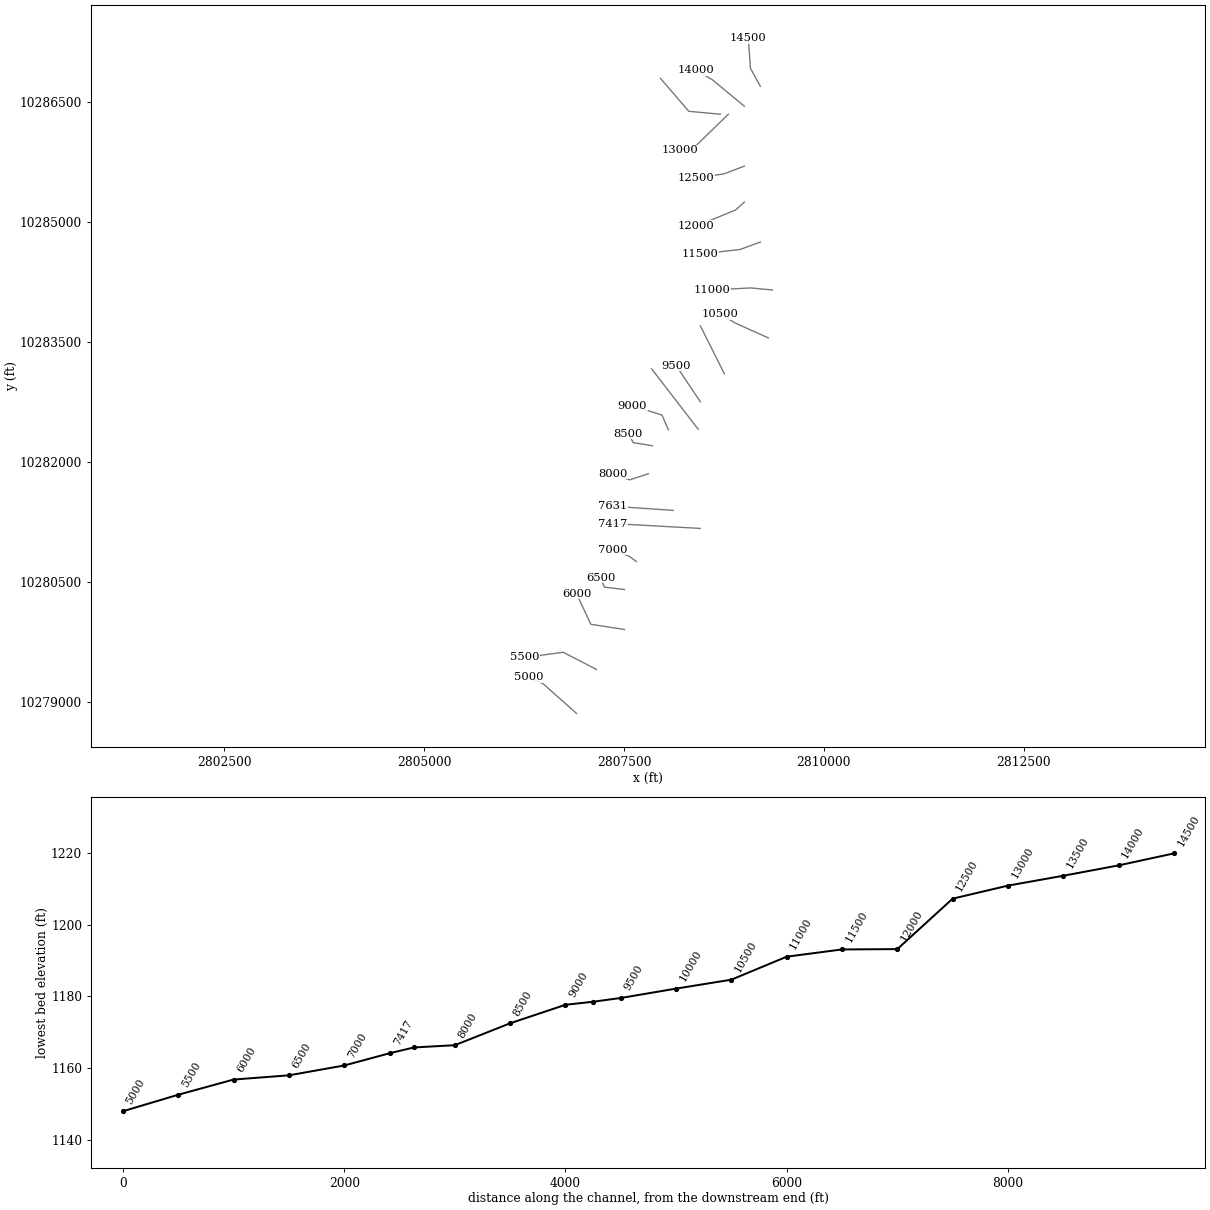
HEC-RAS study BABYHEAD CREEK.prj: BABYHEAD CREEK Base Level Engineering

--- BABYHEAD CREEK.g01 (geometry) --- (continued)

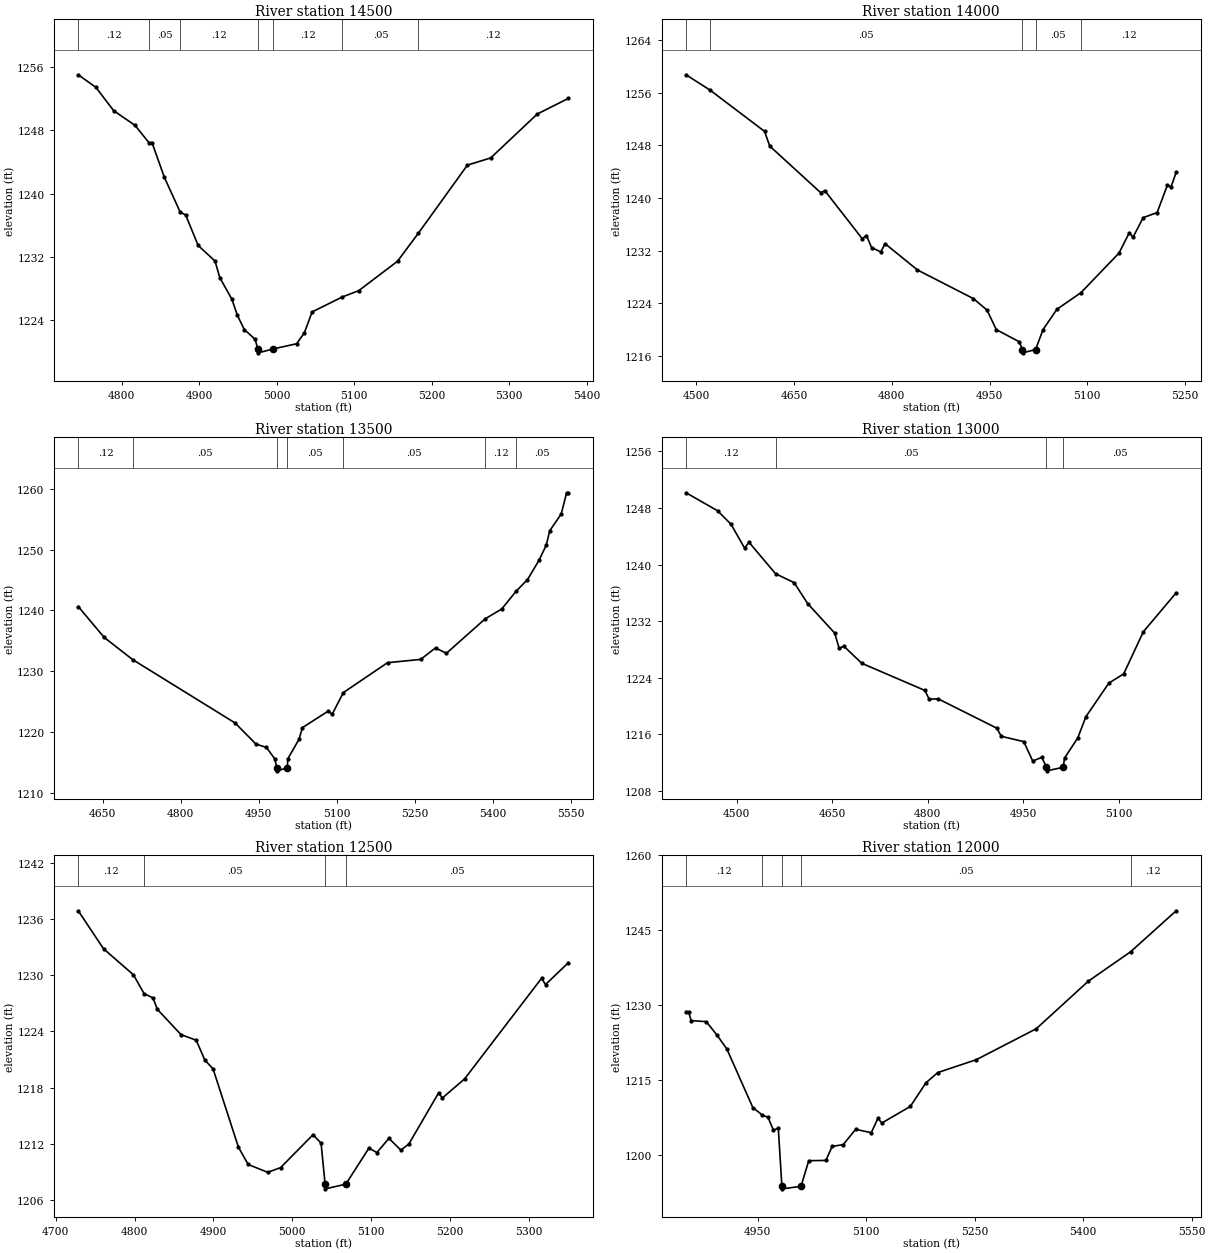
Type RM Length L Ch R = 1 ,14500   ,500,500,500
BEGIN DESCRIPTION:
BABYHEAD CREEK 29.0
END DESCRIPTION:
XS GIS Cut Line= 3
      2809205.69      10286703.1      2809082.01     10286927.58
      2809055.69     10287303.06
#Sta/Elev= 30
  4743.7 1255.05  4766.5 1253.46  4789.4 1250.51  4817.1 1248.64  4834.9 1246.46
  4838.9 1246.47  4854.9 1242.06  4875.4 1237.65  4882.4  1237.3  4898.5 1233.44
  4920.3 1231.46  4926.4 1229.37    4942 1226.64  4949.2 1224.58  4958.1 1222.79
  4972.1 1221.55  4975.5 1220.34    4976 1219.84  4995.7 1220.34  5025.6 1220.99
  5035.6 1222.37  5045.6 1225.02  5084.7 1226.92  5105.8 1227.71  5155.9 1231.44
  5182.9    1235  5246.1 1243.61  5276.2 1244.52  5336.3 1250.08  5376.4 1252.06
#Mann= 7 ,-1 , 0
  4743.7     .12       0  4834.9     .05       0  4875.4     .12       0
  4975.5     .07       0  4995.7     .12       0  5084.7     .05       0
  5182.9     .12       0
Bank Sta=4975.5,4995.7
XS Rating Curve= 0 ,0
Exp/Cntr=0.3,0.1

Type RM Length L Ch R = 1 ,14000   ,500,500,500
BEGIN DESCRIPTION:
BABYHEAD CREEK 28.0
END DESCRIPTION:
XS GIS Cut Line= 3
      2809005.69     10286453.11      2808608.66     10286782.07
      2808405.71      10286903.1
#Sta/Elev= 30
  4484.4 1258.72  4521.1  1256.4  4604.9 1250.12  4612.7  1247.9  4690.8 1240.83
  4697.3 1241.12  4754.7 1233.83  4761.2 1234.31    4769 1232.49  4783.1 1231.82
  4789.8 1233.07  4839.3 1229.09  4925.3 1224.73  4946.1 1222.99  4960.4 1220.02
  4995.6 1218.18  5000.4    1217  5000.9  1216.5  5020.7    1217    5032 1220.02
  5053.4 1223.12  5090.2 1225.63  5148.7 1231.66  5164.3 1234.72  5170.1 1234.05
  5185.7 1237.03  5207.1  1237.8  5222.7 1241.93  5228.5 1241.72  5236.3  1243.9
#Mann= 5 ,-1 , 0
  4484.4     .12       0  4521.1     .05       0  5000.4     .05       0
  5020.7     .05       0  5090.2     .12       0
Bank Sta=5000.4,5020.7
XS Rating Curve= 0 ,0
Exp/Cntr=0.3,0.1

Type RM Length L Ch R = 1 ,13500   ,500,500,500
BEGIN DESCRIPTION:
BABYHEAD CREEK 27.0
END DESCRIPTION:
XS GIS Cut Line= 3
      2808705.73     10286353.11      2808310.43     10286389.81
      2807955.67     10286803.13
#Sta/Elev= 30
    4603 1240.64  4652.7 1235.57  4707.7  1231.9  4904.3 1221.49  4944.5 1218.01
  4964.6 1217.46  4980.7 1215.57  4984.6 1214.11  4985.1 1213.61  5004.9 1214.11
  5005.5 1215.56  5027.2  1218.8  5033.8 1220.72  5083.4 1223.44  5090.9 1222.92
  5112.4 1226.48  5197.3  1231.4    5261 1231.94  5289.5 1233.84  5310.4 1232.94
  5384.8 1238.61  5416.8 1240.24  5444.9 1243.21  5466.2 1245.06  5488.2 1248.22
  5502.4 1250.75    5509 1253.11    5531 1255.85  5541.4 1259.35  5544.7 1259.35
#Mann= 7 ,-1 , 0
    4603     .12       0  4707.7     .05       0  4984.6     .05       0
  5004.9     .05       0  5112.4     .05       0  5384.8     .12       0
  5444.9     .05       0
Bank Sta=4984.6,5004.9
XS Rating Curve= 0 ,0
Exp/Cntr=0.3,0.1

Type RM Length L Ch R = 1 ,13000   ,500,500,500
BEGIN DESCRIPTION:
BABYHEAD CREEK 26.0
END DESCRIPTION:
XS GIS Cut Line= 3
      2808805.68     10286353.11      2808390.23     10285949.25
      2808205.71     10285903.12
#Sta/Elev= 30
  4420.6 1250.16  4470.1 1247.62  4491.2 1245.71  4512.5 1242.34  4519.5 1243.16
  4561.1 1238.72  4590.3 1237.46  4611.6 1234.49    4654 1230.33    4661 1228.16
  4668.2 1228.49  4696.5 1226.06  4795.5 1222.23  4802.4 1220.99  4816.6 1221.03
  4908.6 1216.89  4915.6 1215.74  4950.9 1214.99    4965 1212.24  4979.2 1212.77
  4986.5 1211.36    4987 1210.86  5012.8 1211.36    5015 1212.69  5035.6 1215.49
  5048.5 1218.52  5084.6 1223.27  5107.8 1224.56  5138.7 1230.52  5190.2 1236.02
#Mann= 4 ,-1 , 0
  4420.6     .12       0  4561.1     .05       0  4986.5     .05       0
  5012.8     .05       0
Bank Sta=4986.5,5012.8
XS Rating Curve= 0 ,0
Exp/Cntr=0.3,0.1

Type RM Length L Ch R = 1 ,12500   ,500,500,500
BEGIN DESCRIPTION:
BABYHEAD CREEK 25.0
END DESCRIPTION:
XS GIS Cut Line= 3
      2809005.73     10285703.13      2808751.91     10285607.03
      2808405.69     10285553.11
#Sta/Elev= 30
  4728.6 1236.86  4760.7 1232.81  4798.7 1230.03  4812.1 1228.03  4823.5 1227.57
  4828.9 1226.36    4859 1223.66  4878.3 1223.06  4889.2 1220.95  4899.7    1220
  4931.8 1211.67  4944.2 1209.82    4969 1208.98  4985.3 1209.48  5026.5 1212.99
  5036.7 1212.09  5041.8 1207.72  5042.3 1207.22  5068.1 1207.72  5097.4 1211.56
  5107.5 1211.09  5122.8  1212.6  5137.9 1211.35    5148 1211.99  5185.7 1217.43
  5190.7 1216.91  5218.8 1218.94  5316.4 1229.66  5321.5    1229  5350.4 1231.32
#Mann= 4 ,-1 , 0
  4728.6     .12       0  4812.1     .05       0  5041.8     .03       0
  5068.1     .05       0
Bank Sta=5041.8,5068.1
XS Rating Curve= 0 ,0
Exp/Cntr=0.3,0.1

Type RM Length L Ch R = 1 ,12000   ,500,500,500
BEGIN DESCRIPTION:
BABYHEAD CREEK 24.0
END DESCRIPTION:
XS GIS Cut Line= 3
      2809005.69     10285253.12      2808894.75     10285153.64
      2808405.67     10284953.11
#Sta/Elev= 30
    4851 1228.67  4854.4 1228.67  4858.1 1226.89    4879 1226.68  4893.2 1224.09
  4907.4  1221.2  4943.3 1209.46  4956.4 1207.96  4964.3 1207.49  4971.8 1204.93
  4978.5 1205.33  4983.5 1193.66    4984 1193.16  5009.9 1193.66  5020.6  1198.8
  5044.3 1198.86    5053 1201.66  5068.3 1202.03  5085.5  1205.1  5107.1 1204.41
  5116.2 1207.29  5121.7 1206.36  5161.1 1209.69  5182.7 1214.43    5199 1216.47
  5252.4 1219.06  5335.2 1225.26  5407.1 1234.79  5465.7  1240.7  5528.6 1248.91
#Mann= 5 ,-1 , 0
    4851     .12       0  4956.4     .05       0  4983.5     .03       0
  5009.9     .05       0  5465.7     .12       0
Bank Sta=4983.5,5009.9
XS Rating Curve= 0 ,0
Exp/Cntr=0.3,0.1

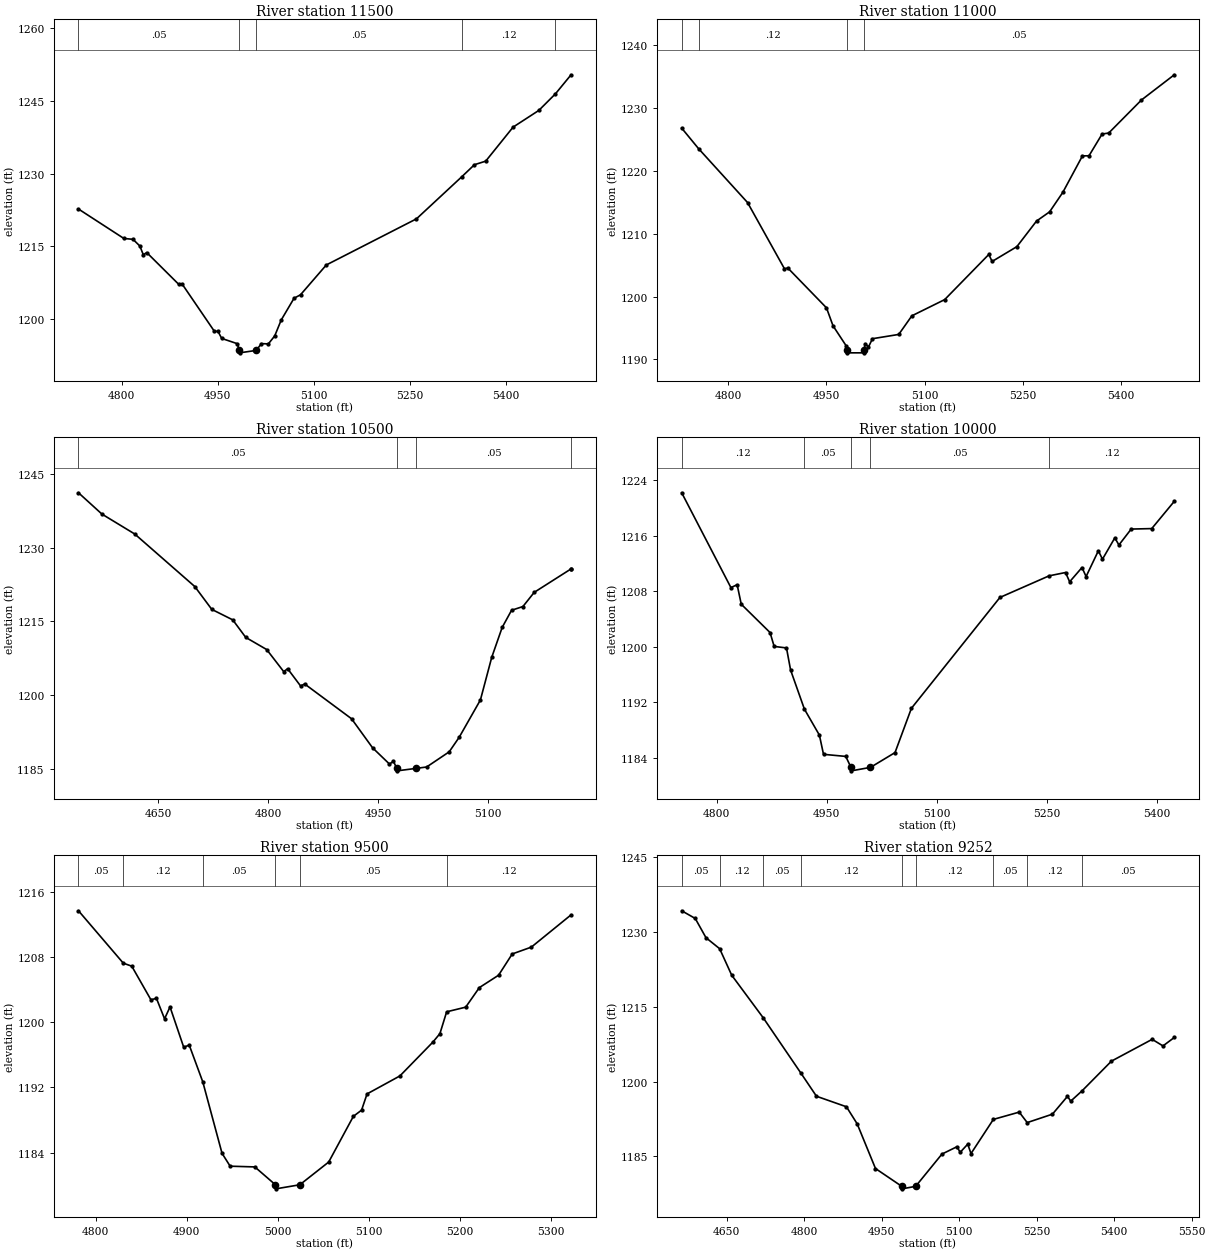
Type RM Length L Ch R = 1 ,11500   ,500,500,500
BEGIN DESCRIPTION:
BABYHEAD CREEK 23.0
END DESCRIPTION:
XS GIS Cut Line= 3
      2809205.69     10284753.11      2808954.35     10284660.69
      2808455.66     10284603.11
#Sta/Elev= 30
  4732.2 1222.69  4803.1 1216.63  4817.4 1216.45  4828.1 1215.07  4833.5 1213.28
  4838.9 1213.72  4889.1 1207.15  4894.5 1207.18  4944.7 1197.48  4950.1 1197.52
    4956 1196.04  4980.5 1194.95  4983.4 1193.57  4983.9 1193.07  5009.9 1193.57
  5018.1 1194.97  5028.9 1194.91  5038.9 1196.56    5049 1199.83  5069.1 1204.32
  5079.2 1205.03  5119.5 1211.17  5260.4 1220.67  5331.4 1229.36    5351 1231.82
  5368.6 1232.55  5411.4 1239.56  5451.6    1243  5477.6 1246.42    5502 1250.34
#Mann= 5 ,-1 , 0
  4732.2     .05       0  4983.4     .05       0  5009.9     .05       0
  5331.4     .12       0  5477.6     .05       0
Bank Sta=4983.4,5009.9
XS Rating Curve= 0 ,0
Exp/Cntr=0.3,0.1

Type RM Length L Ch R = 1 ,11000   ,500,500,500
BEGIN DESCRIPTION:
BABYHEAD CREEK 22.0
END DESCRIPTION:
XS GIS Cut Line= 3
      2809355.68     10284153.11        2809086.     10284178.81
      2808605.69     10284153.11
#Sta/Elev= 30
  4729.1 1226.81  4754.8 1223.55  4829.6 1214.97    4886 1204.42    4891 1204.56
  4950.1 1198.21  4960.1 1195.35  4980.2 1192.16  4980.7 1191.55  4981.2 1191.05
  5006.8 1191.05  5007.3 1191.55  5009.2 1192.51  5014.2 1191.98  5020.3  1193.3
  5060.4 1193.98  5080.4 1196.94  5130.5 1199.52  5197.9 1206.71  5202.9 1205.59
  5240.7 1207.95  5270.7 1212.02  5290.7 1213.49  5310.8 1216.58  5340.8 1222.39
  5350.8 1222.41  5370.8 1225.87  5380.9 1226.03  5430.9 1231.29    5481  1235.3
#Mann= 4 ,-1 , 0
  4729.1     .05       0  4754.8     .12       0  4980.7     .03       0
  5007.3     .05       0
Bank Sta=4980.7,5007.3
XS Rating Curve= 0 ,0
Exp/Cntr=0.3,0.1

Type RM Length L Ch R = 1 ,10500   ,500,500,500
BEGIN DESCRIPTION:
BABYHEAD CREEK 21.0
END DESCRIPTION:
XS GIS Cut Line= 3
      2809305.71      10283553.1       2808887.6     10283741.26
      2808705.65     10283853.14
#Sta/Elev= 30
  4541.5 1241.13  4573.5  1236.8  4618.3 1232.75  4700.2 1222.08  4723.4 1217.44
    4752 1215.31  4769.7 1211.75  4798.3 1209.28  4821.5  1204.8  4826.9 1205.38
  4844.6 1201.87  4850.1 1202.29  4914.1 1195.22  4942.7 1189.33  4965.8 1186.02
  4971.3 1186.58  4975.7 1185.14  4976.2 1184.64  5002.3 1185.14  5016.5 1185.42
  5047.3  1188.5  5060.9 1191.45  5089.9 1199.04  5105.3 1207.68  5119.6 1213.78
  5132.4 1217.26  5147.9 1218.02  5163.3  1220.9  5213.1 1225.62  5213.6 1225.62
#Mann= 4 ,-1 , 0
  4541.5     .05       0  4975.7     .03       0  5002.3     .05       0
  5213.1     .12       0
Bank Sta=4975.7,5002.3
XS Rating Curve= 0 ,0
Exp/Cntr=0.3,0.1

Type RM Length L Ch R = 1 ,10000   ,500,500,500
BEGIN DESCRIPTION:
BABYHEAD CREEK 20.0
END DESCRIPTION:
XS GIS Cut Line= 3
      2808755.67     10283103.15      2808645.41     10283324.62
      2808455.68     10283703.13
#Sta/Elev= 30
  4752.6 1222.22  4819.6 1208.56  4828.1 1208.97  4833.7 1206.16  4872.9 1202.08
  4878.5 1200.08  4895.3 1199.86  4900.9 1196.67  4919.7 1191.04  4940.1  1187.3
  4945.7 1184.53    4976 1184.23  4983.1 1182.65  4983.6 1182.15  5009.7 1182.65
  5043.1 1184.78  5065.4 1191.16    5186 1207.14  5252.9 1210.25  5275.3 1210.73
  5280.9 1209.39  5297.7 1211.45  5303.3 1210.15    5320 1213.86  5325.6 1212.65
  5342.4 1215.72    5348  1214.7  5364.7 1216.99  5392.7 1217.06  5423.4 1220.99
#Mann= 5 ,-1 , 0
  4752.6     .12       0  4919.7     .05       0  4983.1     .05       0
  5009.7     .05       0  5252.9     .12       0
Bank Sta=4983.1,5009.7
XS Rating Curve= 0 ,0
Exp/Cntr=0.3,0.1

Type RM Length L Ch R = 1 ,9500    ,248,248,248
BEGIN DESCRIPTION:
BABYHEAD CREEK 19.0
END DESCRIPTION:
XS GIS Cut Line= 3
      2808455.69      10282753.1      2808333.83     10282934.71
      2808155.71     10283203.07
#Sta/Elev= 30
  4781.3 1213.67  4830.5 1207.24  4839.8 1206.87  4860.8 1202.75  4866.9 1202.92
  4875.8 1200.41  4881.8 1201.87  4896.8 1196.93  4902.9 1197.18  4917.8 1192.66
  4938.9  1183.9  4947.8 1182.32  4974.9 1182.23  4997.5 1180.04    4998 1179.54
  5024.3 1180.04    5056 1182.83  5083.1 1188.44  5092.1  1189.2  5098.1 1191.19
  5134.2  1193.4  5170.3 1197.54  5178.1 1198.59  5185.5 1201.27  5206.4 1201.84
  5221.4 1204.24  5242.5 1205.76  5257.5 1208.37  5278.5 1209.21  5322.1 1213.17
#Mann= 6 ,-1 , 0
  4781.3     .05       0  4830.5     .12       0  4917.8     .05       0
  4997.5     .05       0  5024.3     .05       0  5185.5     .12       0
Bank Sta=4997.5,5024.3
XS Rating Curve= 0 ,0
Exp/Cntr=0.3,0.1

Type RM Length L Ch R = 1 ,9252    ,252,252,252
BEGIN DESCRIPTION:
Mapping XS c34c898a
END DESCRIPTION:
XS GIS Cut Line= 2
      2808428.39     10282409.64       2807846.8     10283164.85
#Sta/Elev= 30
  4563.2 1234.24  4589.4  1232.7  4610.2 1228.84  4636.6 1226.64    4660 1221.32
  4721.2 1212.75  4793.4 1201.77    4824 1197.06    4882 1194.95  4902.8 1191.52
  4938.2 1182.57  4989.1    1179  4989.6  1178.5  5015.9    1179  5066.8 1185.47
  5095.8 1186.94  5102.1 1185.82  5116.7 1187.46    5123 1185.57  5166.3 1192.42
  5216.3 1193.88  5231.8 1191.78  5280.6 1193.47  5309.7 1197.04    5316 1196.08
  5337.8 1198.13  5394.8  1204.1  5473.6 1208.47  5494.5 1207.15  5516.4 1208.84
#Mann= 9 ,-1 , 0
  4563.2     .05       0  4636.6     .12       0  4721.2     .05       0
  4793.4     .12       0  4989.1     .07       0  5015.9     .12       0
  5166.3     .05       0  5231.8     .12       0  5337.8     .05       0
Bank Sta=4989.1,5015.9
XS Rating Curve= 0 ,0
Exp/Cntr=0.3,0.1

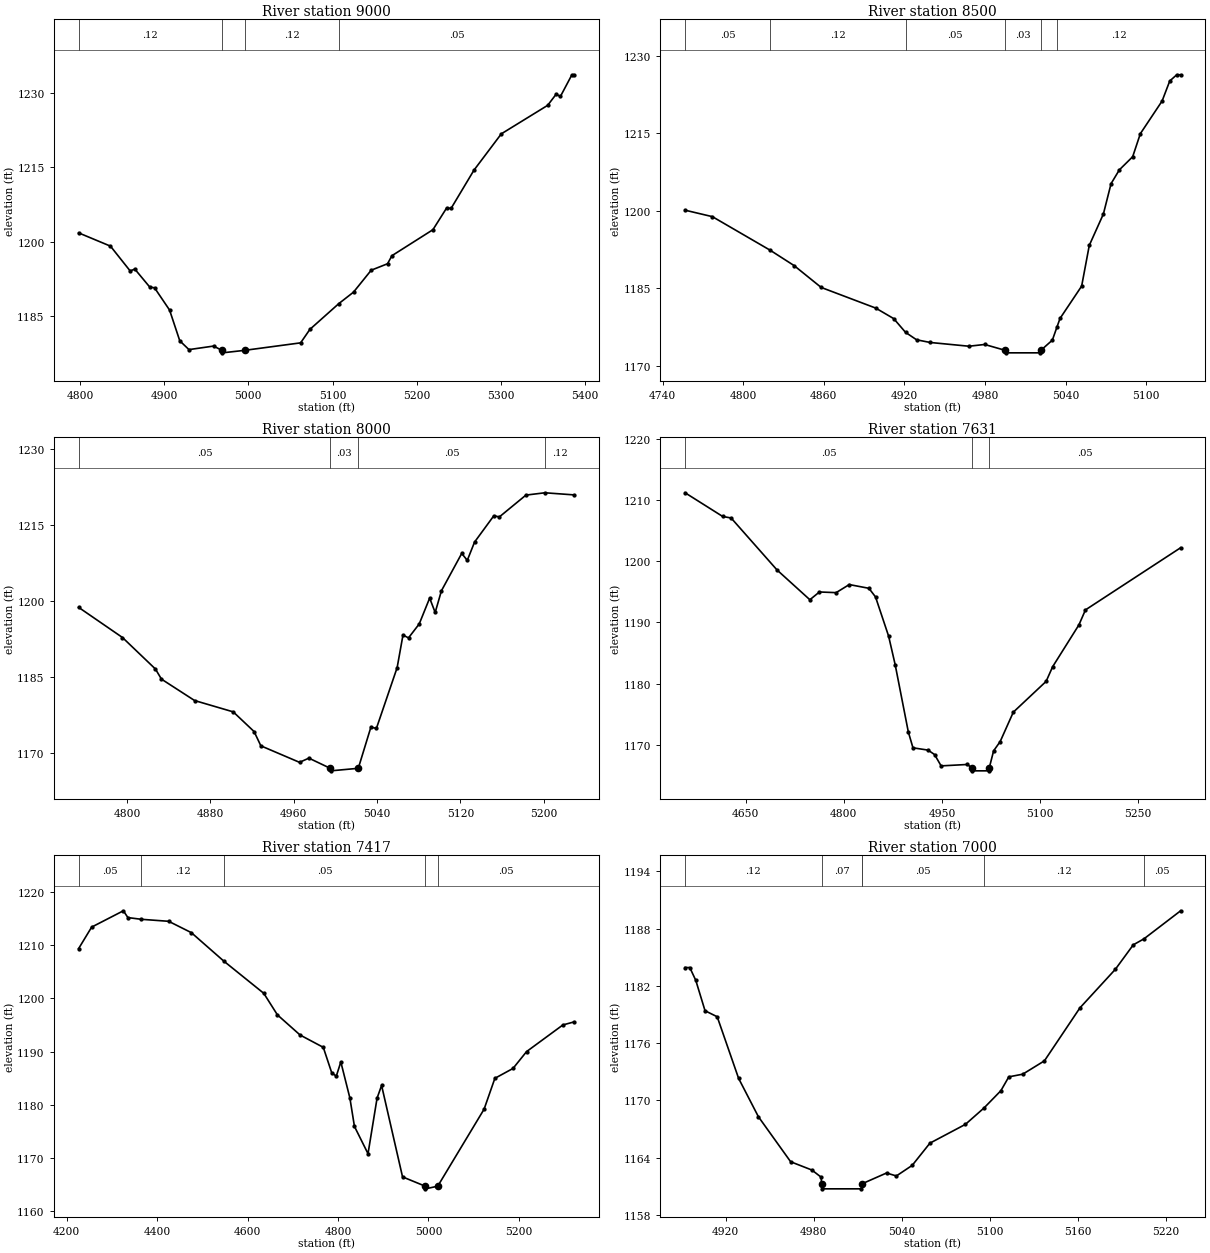
Type RM Length L Ch R = 1 ,9000    ,500,500,500
BEGIN DESCRIPTION:
BABYHEAD CREEK 18.0
END DESCRIPTION:
XS GIS Cut Line= 3
      2808055.68     10282403.11      2807974.92     10282587.72
      2807605.64     10282703.13
#Sta/Elev= 30
  4798.5 1201.77  4836.3  1199.1  4859.7 1194.11  4865.2 1194.49  4883.1 1190.84
  4888.6 1190.73  4906.5 1186.24  4918.6 1180.06  4929.5 1178.29  4958.7    1179
  4968.7 1178.14  4969.2 1177.64  4995.5 1178.14  5062.1 1179.65  5073.1 1182.36
  5107.5 1187.55  5124.9 1189.85  5145.9 1194.26  5165.3 1195.56  5170.5 1197.18
  5219.2 1202.41  5235.5 1206.79  5240.7 1206.68  5267.9 1214.38  5300.4 1221.69
  5355.4 1227.42  5365.4 1229.64  5370.6 1229.22  5384.2 1233.57  5386.9 1233.57
#Mann= 4 ,-1 , 0
  4798.5     .12       0  4968.7     .07       0  4995.5     .12       0
  5107.5     .05       0
Bank Sta=4968.7,4995.5
XS Rating Curve= 0 ,0
Exp/Cntr=0.3,0.1

Type RM Length L Ch R = 1 ,8500    ,500,500,500
BEGIN DESCRIPTION:
BABYHEAD CREEK 17.0
END DESCRIPTION:
XS GIS Cut Line= 3
      2807855.67     10282203.11      2807615.71     10282242.72
      2807555.66     10282353.15
#Sta/Elev= 30
  4756.8 1200.12  4777.1 1198.87  4820.1 1192.37  4837.9  1189.4  4858.1 1185.16
  4898.7 1181.16  4912.1 1179.12  4920.9 1176.46  4929.1 1175.02  4939.2  1174.5
  4968.1 1173.77  4979.8 1174.11  4994.9 1172.99  4995.4 1172.49  5021.2 1172.49
  5021.7 1172.99  5030.2 1174.95  5033.6 1177.46  5035.9 1179.15    5052 1185.41
  5057.7 1193.31  5068.2 1199.39  5073.9 1205.26  5080.1 1207.94    5090 1210.48
  5095.7 1214.94  5111.9 1221.27  5117.6 1225.15  5122.8 1226.35  5125.7 1226.35
#Mann= 6 ,-1 , 0
  4756.8     .05       0  4820.1     .12       0  4920.9     .05       0
  4994.9     .03       0  5021.7     .05       0  5033.6     .12       0
Bank Sta=4994.9,5021.7
XS Rating Curve= 0 ,0
Exp/Cntr=0.3,0.1

Type RM Length L Ch R = 1 ,8000    ,369,369,369
BEGIN DESCRIPTION:
BABYHEAD CREEK 16.0
END DESCRIPTION:
XS GIS Cut Line= 3
      2807805.66      10281853.1      2807571.56     10281776.22
      2807355.65     10281853.12
#Sta/Elev= 30
  4753.6 1198.68  4795.7 1192.72  4827.3  1186.5  4833.1  1184.5  4864.9 1180.27
    4902 1178.03    4922 1174.14  4928.5 1171.32  4965.6 1168.06  4974.6 1168.89
  4995.1 1166.88  4995.6 1166.38    5022 1166.88  5034.1 1175.01  5039.4 1174.77
  5059.3 1186.78  5064.9 1193.21  5070.2 1192.65  5080.5 1195.41  5090.5 1200.51
  5095.8 1197.67  5101.8 1201.96  5121.3 1209.34  5126.6 1207.96  5133.6 1211.58
  5152.1 1216.78  5157.4 1216.55  5182.9 1220.86  5201.1 1221.32  5229.2  1220.9
#Mann= 4 ,-1 , 0
  4753.6     .05       0  4995.1     .03       0    5022     .05       0
  5201.1     .12       0
Bank Sta=4995.1,5022
XS Rating Curve= 0 ,0
Exp/Cntr=0.3,0.1

Type RM Length L Ch R = 1 ,7631    ,214,214,214
BEGIN DESCRIPTION:
Mapping XS 897ebe65
END DESCRIPTION:
XS GIS Cut Line= 2
      2808115.86     10281394.02      2807360.65     10281446.11
#Sta/Elev= 30
  4557.7 1211.19  4615.1 1207.32    4628 1207.07  4698.2 1198.57  4748.3 1193.71
  4762.9 1194.98  4788.4 1194.87  4808.5 1196.19  4838.5 1195.58  4848.6 1194.17
  4868.6 1187.76  4878.6 1183.11  4898.7 1172.11  4905.8 1169.51  4928.8 1169.14
  4938.8 1168.41  4948.8 1166.56  4988.9 1166.79  4995.5 1166.25    4996 1165.75
  5021.9 1165.75  5022.4 1166.25    5029 1169.02    5039 1170.53  5059.1 1175.34
  5109.2 1180.37  5119.2 1182.77  5159.3  1189.6  5169.3 1192.05  5314.7 1202.21
#Mann= 3 ,-1 , 0
  4557.7     .05       0  4995.5     .05       0  5022.4     .05       0
Bank Sta=4995.5,5022.4
XS Rating Curve= 0 ,0
Exp/Cntr=0.3,0.1

Type RM Length L Ch R = 1 ,7417    ,417,417,417
BEGIN DESCRIPTION:
Mapping XS d0584458
END DESCRIPTION:
XS GIS Cut Line= 2
       2808454.4     10281168.33      2807360.69     10281229.09
#Sta/Elev= 30
  4226.7 1209.39  4255.5 1213.43  4325.6  1216.5  4335.6 1215.22    4365  1214.9
  4425.7 1214.52  4475.8 1212.39  4547.5 1207.04    4636 1200.97  4666.1 1196.92
  4716.2 1193.13  4767.5 1190.81  4786.3 1185.99  4796.3  1185.4  4806.3 1188.06
  4826.3 1181.28  4836.4 1175.93  4866.4  1170.8  4886.4 1181.25  4896.4 1183.64
  4942.7 1166.44  4992.8 1164.69  4993.3 1164.19  5020.5 1164.69    5123 1179.18
  5146.8 1184.98  5186.9 1186.84  5216.9 1190.01  5297.1 1195.02  5322.1  1195.6
#Mann= 5 ,-1 , 0
  4226.7     .05       0    4365     .12       0  4547.5     .05       0
  4992.8     .05       0  5020.5     .05       0
Bank Sta=4992.8,5020.5
XS Rating Curve= 0 ,0
Exp/Cntr=0.3,0.1

Type RM Length L Ch R = 1 ,7000    ,500,500,500
BEGIN DESCRIPTION:
BABYHEAD CREEK 14.0
END DESCRIPTION:
XS GIS Cut Line= 3
      2807655.72     10280753.08      2807569.49     10280817.61
      2807355.66     10280903.12
#Sta/Elev= 30
  4892.3 1183.92  4895.5 1183.92  4899.6 1182.57  4905.9 1179.39  4914.2 1178.76
  4928.8  1172.3  4942.3 1168.28  4964.3 1163.56  4978.8 1162.69  4985.1 1161.94
  4985.4 1161.22  4985.9 1160.72  5012.6 1160.72  5013.1 1161.22  5013.3 1161.27
  5029.7 1162.38  5036.4 1162.07  5047.2 1163.18  5059.3 1165.51  5083.5 1167.48
  5096.2  1169.2  5107.7 1171.01  5113.1 1172.46  5122.6 1172.74  5137.4 1174.14
  5161.6 1179.69  5185.8 1183.74    5198  1186.3  5205.3 1186.93  5230.3 1189.87
#Mann= 6 ,-1 , 0
  4892.3     .12       0  4985.4     .07       0  5013.1     .12       0
  5013.3     .05       0  5096.2     .12       0  5205.3     .05       0
Bank Sta=4985.4,5013.1
XS Rating Curve= 0 ,0
Exp/Cntr=0.3,0.1

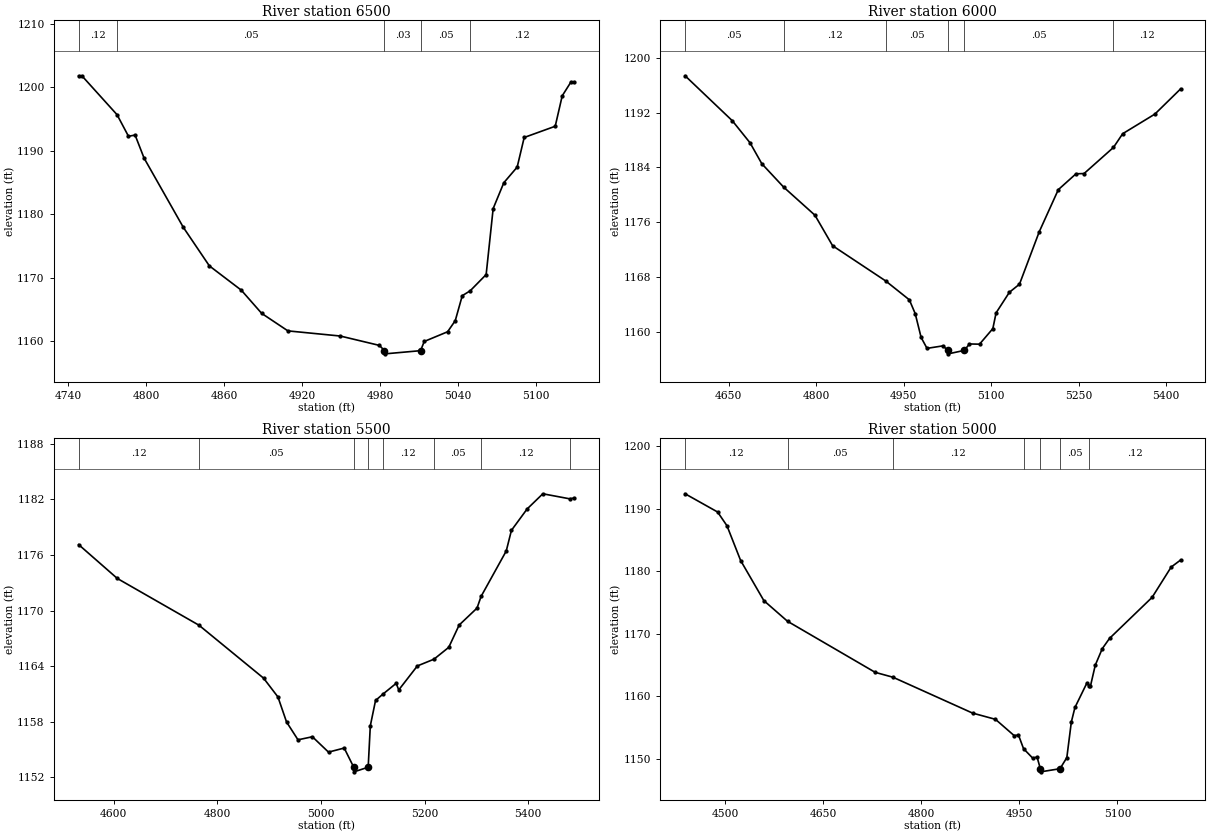
Type RM Length L Ch R = 1 ,6500    ,500,500,500
BEGIN DESCRIPTION:
BABYHEAD CREEK 13.0
END DESCRIPTION:
XS GIS Cut Line= 3
       2807505.7     10280403.11      2807255.43     10280433.44
      2807205.68     10280553.12
#Sta/Elev= 30
  4747.9 1201.83  4750.4 1201.83  4777.5 1195.69  4786.3 1192.29  4791.4 1192.48
  4798.3 1188.85  4828.5 1177.94  4848.6 1171.85  4873.2 1168.02  4888.9 1164.36
  4909.1  1161.6  4949.4 1160.79  4979.6 1159.31  4983.5 1158.48    4984 1157.98
  5011.3 1158.48  5014.1 1159.93  5032.1 1161.46    5038 1163.21  5043.4 1167.15
  5049.5 1167.92  5061.8 1170.48  5067.2 1180.89  5075.4 1184.96  5085.7 1187.43
  5091.1  1192.1    5115 1193.87  5120.4 1198.67  5126.9 1200.78  5129.6 1200.78
#Mann= 5 ,-1 , 0
  4747.9     .12       0  4777.5     .05       0  4983.5     .03       0
  5011.3     .05       0  5049.5     .12       0
Bank Sta=4983.5,5011.3
XS Rating Curve= 0 ,0
Exp/Cntr=0.3,0.1

Type RM Length L Ch R = 1 ,6000    ,500,500,500
BEGIN DESCRIPTION:
BABYHEAD CREEK 12.0
END DESCRIPTION:
XS GIS Cut Line= 3
      2807505.73     10279903.11      2807085.93     10279968.12
      2806905.68     10280353.11
#Sta/Elev= 30
  4575.2 1197.36  4656.2  1190.8  4686.6 1187.58  4706.8 1184.53  4744.2 1181.12
  4797.9 1177.02  4828.2 1172.57  4919.1 1167.44  4959.8 1164.68  4969.9 1162.66
    4980 1159.19  4990.1  1157.6  5017.2 1157.96  5026.1  1157.3  5026.6  1156.8
    5054  1157.3  5062.9 1158.24  5080.2 1158.21    5103 1160.48  5108.6 1162.78
  5131.4 1165.78  5148.7 1166.96  5182.6 1174.61  5215.3 1180.75  5245.6 1183.06
  5259.5  1183.1  5309.9 1186.91  5325.7 1188.91  5380.9 1191.77  5425.1 1195.45
#Mann= 6 ,-1 , 0
  4575.2     .05       0  4744.2     .12       0  4919.1     .05       0
  5026.1     .03       0    5054     .05       0  5309.9     .12       0
Bank Sta=5026.1,5054
XS Rating Curve= 0 ,0
Exp/Cntr=0.3,0.1

Type RM Length L Ch R = 1 ,5500    ,500,500,500
BEGIN DESCRIPTION:
BABYHEAD CREEK 11.0
END DESCRIPTION:
XS GIS Cut Line= 3
      2807155.66     10279403.13      2806739.98     10279617.93
      2806255.69     10279553.11
#Sta/Elev= 30
  4532.1 1177.12  4606.8 1173.46  4764.4 1168.41  4889.1 1162.69  4916.8 1160.66
  4933.4 1157.96  4955.5 1156.03  4983.3 1156.36  5014.4  1154.7  5044.7 1155.14
  5063.1 1153.07  5063.6 1152.57    5091 1153.07  5095.1 1157.54  5105.2 1160.28
  5118.9 1160.94    5145 1162.13    5150 1161.42  5185.9 1164.01    5218 1164.74
  5246.5 1166.02  5266.6 1168.43  5301.1 1170.26  5308.9 1171.52  5357.5 1176.43
  5367.5 1178.66  5397.8 1180.97  5428.1 1182.61  5480.5 1182.06  5488.6 1182.16
#Mann= 8 ,-1 , 0
  4532.1     .12       0  4764.4     .05       0  5063.1     .03       0
    5091     .05       0  5118.9     .12       0    5218     .05       0
  5308.9     .12       0  5480.5     .05       0
Bank Sta=5063.1,5091
XS Rating Curve= 0 ,0
Exp/Cntr=0.3,0.1

Type RM Length L Ch R = 1 ,5000    ,500,500,500
BEGIN DESCRIPTION:
BABYHEAD CREEK 10.0
END DESCRIPTION:
XS GIS Cut Line= 3
      2806905.68     10278853.11      2806486.48     10279225.93
      2806305.67     10279303.12
#Sta/Elev= 30
    4439 1192.35  4488.7 1189.44    4503 1187.25  4523.9  1181.7  4559.4  1175.3
  4595.6    1172  4729.6 1163.85  4756.8 1163.07  4878.4 1157.35  4913.5 1156.35
    4942 1153.76  4948.7 1153.84  4956.4 1151.67  4970.4 1150.16  4977.1 1150.33
  4982.1 1148.47  4982.6 1147.97  5012.2 1148.47  5022.6 1150.24  5029.5 1155.93
    5035 1158.24  5053.1 1162.11    5057 1161.75  5058.6  1161.6  5066.1    1165
  5076.8 1167.63  5087.9 1169.27    5153 1175.82  5182.1 1180.65  5196.6 1181.78
#Mann= 7 ,-1 , 0
    4439     .12       0  4595.6     .05       0  4756.8     .12       0
  4956.4     .05       0  4982.1     .05       0  5012.2     .05       0
    5057     .12       0
Bank Sta=4982.1,5012.2
XS Rating Curve= 0 ,0
Exp/Cntr=0.3,0.1