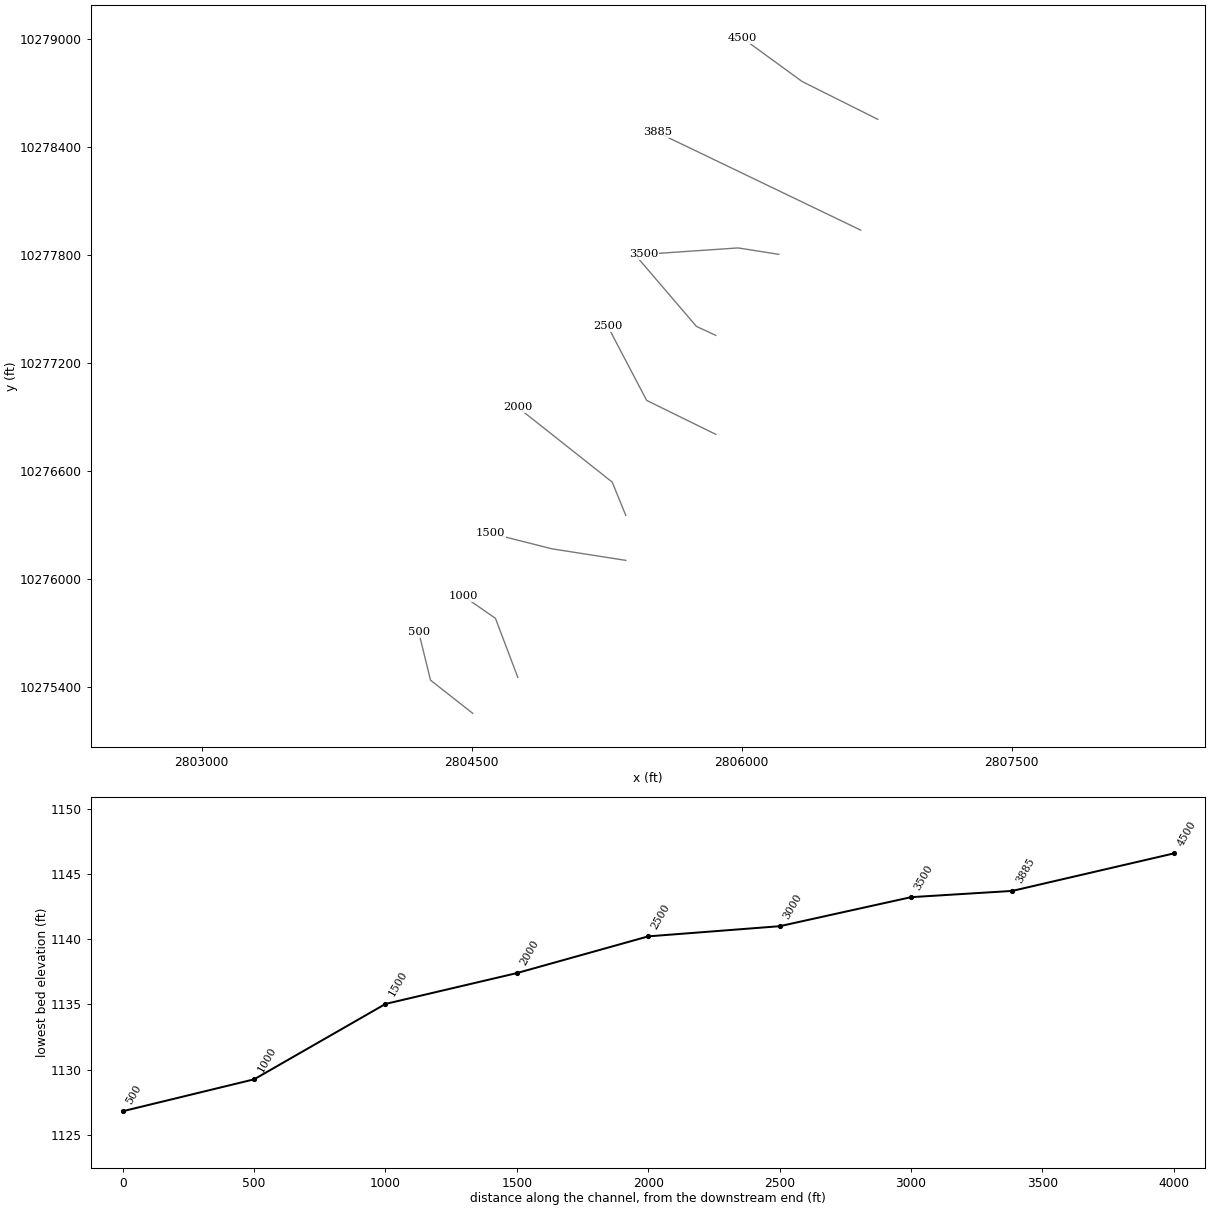
HEC-RAS study BABYHEAD CREEK.prj: BABYHEAD CREEK Base Level Engineering

--- BABYHEAD CREEK.g01 (geometry) --- (continued)

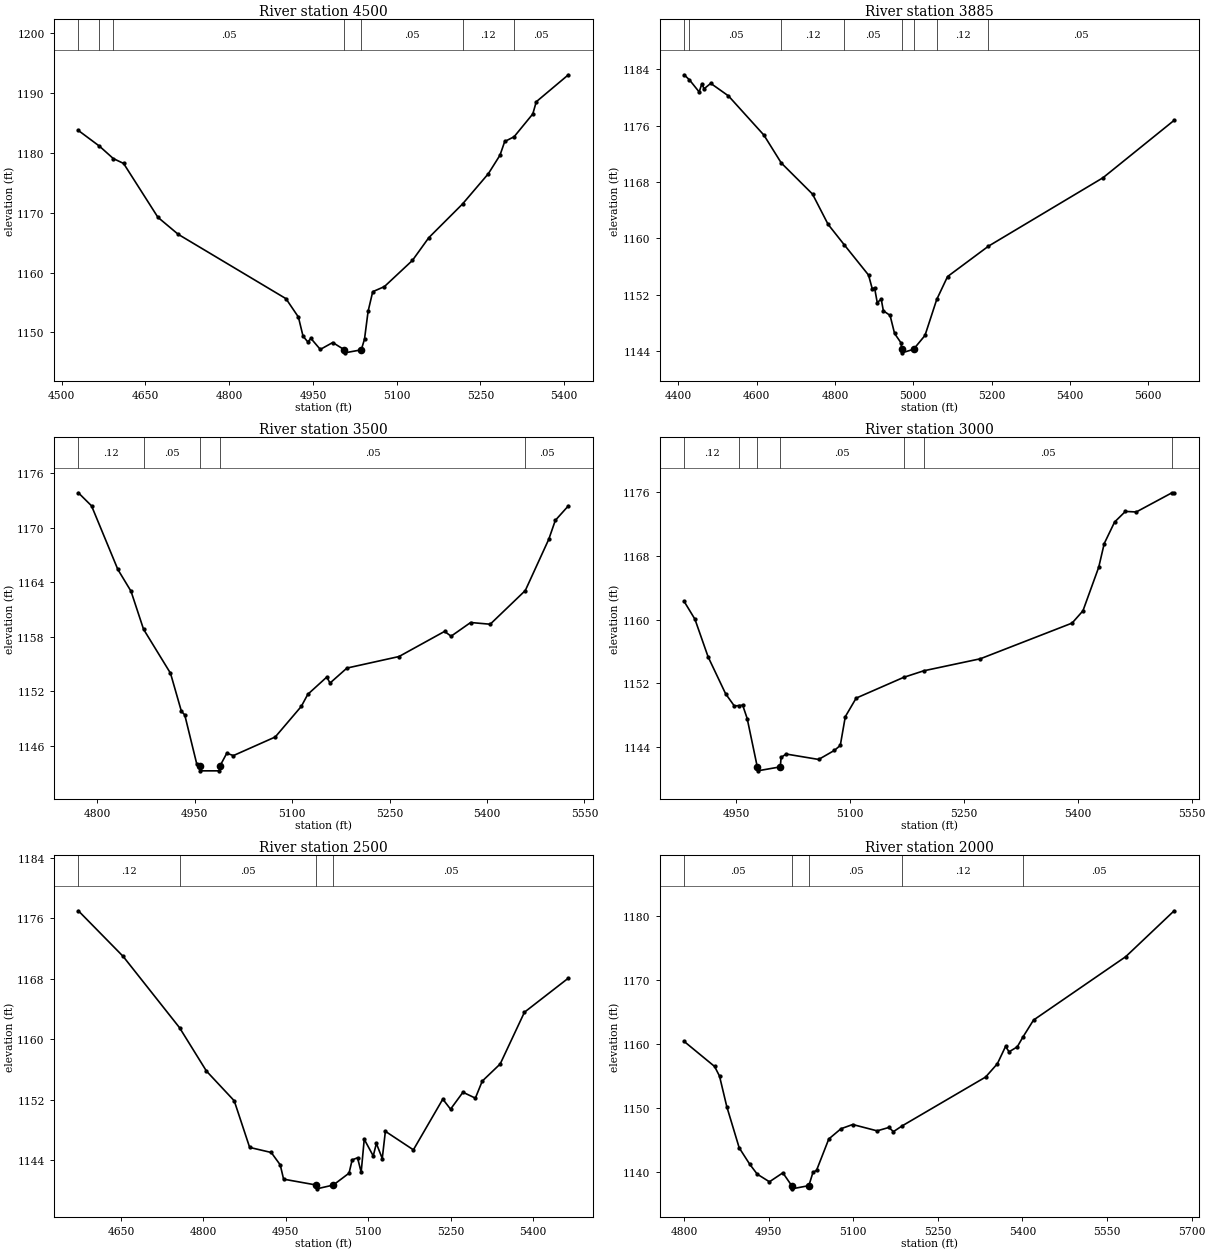
Type RM Length L Ch R = 1 ,4500    ,615,615,615
BEGIN DESCRIPTION:
BABYHEAD CREEK 9.0
END DESCRIPTION:
XS GIS Cut Line= 3
      2806755.67     10278553.12      2806335.16     10278763.29
       2806005.7      10279003.1
#Sta/Elev= 30
  4529.9  1183.7  4567.7 1181.08  4592.5 1179.01  4610.9  1178.2  4672.4 1169.21
  4708.8 1166.37  4901.7 1155.64    4924 1152.57  4932.3 1149.38  4940.8 1148.43
  4946.4 1149.01  4963.2 1147.17  4985.5 1148.32  5006.5  1147.1    5007  1146.6
  5036.6  1147.1  5042.4 1148.89  5048.8 1153.52  5057.1  1156.8    5078 1157.65
  5128.2 1162.02  5157.5 1165.81  5217.9 1171.43  5264.2 1176.49    5285 1179.57
  5293.5 1181.86  5310.3 1182.65  5343.8 1186.46    5350 1188.49  5407.5 1192.99
#Mann= 7 ,-1 , 0
  4529.9     .05       0  4567.7     .12       0  4592.5     .05       0
  5006.5     .05       0  5036.6     .05       0  5217.9     .12       0
  5310.3     .05       0
Bank Sta=5006.5,5036.6
XS Rating Curve= 0 ,0
Exp/Cntr=0.3,0.1

Type RM Length L Ch R = 1 ,3885    ,385,385,385
BEGIN DESCRIPTION:
Mapping XS 3cf20cec
END DESCRIPTION:
XS GIS Cut Line= 2
      2806660.32      10277937.9      2805531.86     10278480.42
#Sta/Elev= 30
  4414.6 1183.23  4428.3  1182.5    4453 1180.79  4459.9 1181.96  4465.5 1181.24
  4482.6 1182.01  4527.8 1180.23  4618.4 1174.66  4662.8  1170.7  4742.6 1166.28
  4782.4 1161.98  4823.9 1159.06  4885.8 1154.77  4895.5 1152.77  4901.1 1152.98
    4908 1150.87  4918.2 1151.34  4923.7 1149.69  4940.8 1149.04  4952.3 1146.47
    4969 1145.12  4970.5 1144.22    4971 1143.72  5000.7 1144.22    5030 1146.19
    5060  1151.3  5087.7 1154.56  5192.3 1158.88  5484.9  1168.6  5666.7 1176.76
#Mann= 8 ,-1 , 0
  4414.6     .12       0  4428.3     .05       0  4662.8     .12       0
  4823.9     .05       0  4970.5     .03       0  5000.7     .05       0
    5060     .12       0  5192.3     .05       0
Bank Sta=4970.5,5000.7
XS Rating Curve= 0 ,0
Exp/Cntr=0.3,0.1

Type RM Length L Ch R = 1 ,3500    ,500,500,500
BEGIN DESCRIPTION:
BABYHEAD CREEK 7.0
END DESCRIPTION:
XS GIS Cut Line= 3
      2806205.72     10277803.11      2805979.62     10277838.82
      2805455.64     10277803.11
#Sta/Elev= 30
  4771.1 1173.87  4791.4 1172.43  4831.9 1165.42  4852.1 1163.03  4871.4 1158.84
  4912.9 1153.99  4929.7 1149.79  4934.8 1149.41  4953.4 1143.97  4958.5 1143.74
    4959 1143.24  4988.3 1143.24  4988.8 1143.74  4999.5 1145.18  5009.7 1144.92
  5074.1 1146.97  5114.2 1150.34  5124.2 1151.67  5153.4 1153.57  5158.4 1152.91
  5184.4 1154.56  5264.5 1155.83  5334.7  1158.6  5344.7 1158.07  5374.8 1159.58
  5404.9 1159.39  5458.9  1163.1  5495.1 1168.76  5505.1 1170.83  5525.2 1172.43
#Mann= 5 ,-1 , 0
  4771.1     .12       0  4871.4     .05       0  4958.5     .07       0
  4988.8     .05       0  5458.9     .05       0
Bank Sta=4958.5,4988.8
XS Rating Curve= 0 ,0
Exp/Cntr=0.3,0.1

Type RM Length L Ch R = 1 ,3000    ,500,500,500
BEGIN DESCRIPTION:
BABYHEAD CREEK 6.0
END DESCRIPTION:
XS GIS Cut Line= 3
      2805855.66     10277353.12      2805748.34     10277402.65
      2805405.72     10277803.07
#Sta/Elev= 30
  4881.8 1162.28    4896 1160.05  4913.4 1155.31  4936.4 1150.69  4947.9 1149.15
  4954.2 1149.21  4958.9 1149.25  4964.8 1147.58  4978.1 1141.51  4978.6 1141.01
  5008.4 1141.51  5009.5  1142.7  5016.1 1143.12  5058.9 1142.44  5079.7 1143.58
  5087.4  1144.2    5094 1147.81  5108.3 1150.14  5170.9 1152.75  5197.3 1153.57
  5271.8 1155.08  5392.6 1159.56  5406.9  1161.1  5427.7 1166.58  5434.9 1169.54
  5448.6 1172.25  5462.8 1173.58  5477.1 1173.51  5524.1 1175.92    5527 1175.92
#Mann= 7 ,-1 , 0
  4881.8     .12       0  4954.2     .05       0  4978.1     .03       0
  5008.4     .05       0  5170.9     .12       0  5197.3     .05       0
  5524.1     .12       0
Bank Sta=4978.1,5008.4
XS Rating Curve= 0 ,0
Exp/Cntr=0.3,0.1

Type RM Length L Ch R = 1 ,2500    ,500,500,500
BEGIN DESCRIPTION:
BABYHEAD CREEK 5.0
END DESCRIPTION:
XS GIS Cut Line= 3
      2805855.72      10276803.1      2805471.64     10276991.74
      2805255.69      10277403.1
#Sta/Elev= 30
  4572.1 1177.02  4653.6 1170.99  4756.4 1161.55  4805.4 1155.81    4856 1151.88
  4884.1 1145.71  4923.4 1145.04  4939.8  1143.4  4945.9 1141.51  5005.8 1140.73
  5006.3 1140.23  5036.3 1140.73  5065.1  1142.3  5070.8 1144.06  5080.6 1144.34
  5087.2 1142.42  5092.8 1146.79  5109.2 1144.58  5114.9 1146.24  5125.6 1144.24
  5131.3 1147.84  5182.3 1145.39  5235.9  1152.1    5250 1150.77  5272.6 1153.01
  5295.2 1152.23  5307.7 1154.48  5340.4 1156.75  5384.6  1163.6  5464.6 1168.11
#Mann= 4 ,-1 , 0
  4572.1     .12       0  4756.4     .05       0  5005.8     .05       0
  5036.3     .05       0
Bank Sta=5005.8,5036.3
XS Rating Curve= 0 ,0
Exp/Cntr=0.3,0.1

Type RM Length L Ch R = 1 ,2000    ,500,500,500
BEGIN DESCRIPTION:
BABYHEAD CREEK 4.0
END DESCRIPTION:
XS GIS Cut Line= 3
      2805355.67     10276353.15      2805280.22     10276537.93
      2804755.65     10276953.14
#Sta/Elev= 30
  4800.4 1160.42  4854.4 1156.51  4863.1 1155.01    4876 1150.24    4898 1143.81
  4916.6 1141.26    4930  1139.7  4951.6 1138.51  4975.4 1139.91    4991 1137.91
  4991.5 1137.41  5021.5 1137.91  5028.7 1139.97  5035.1  1140.3  5056.8 1145.19
  5078.4 1146.79  5099.2 1147.45  5142.5 1146.46  5163.3 1146.99  5171.4 1146.34
  5187.3 1147.26  5334.8 1154.86  5355.6 1156.93  5370.1 1159.63  5376.4  1158.8
  5390.9 1159.57  5400.7 1161.07  5419.7 1163.75  5583.2 1173.65    5669 1180.81
#Mann= 5 ,-1 , 0
  4800.4     .05       0    4991     .03       0  5021.5     .05       0
  5187.3     .12       0  5400.7     .05       0
Bank Sta=4991,5021.5
XS Rating Curve= 0 ,0
Exp/Cntr=0.3,0.1

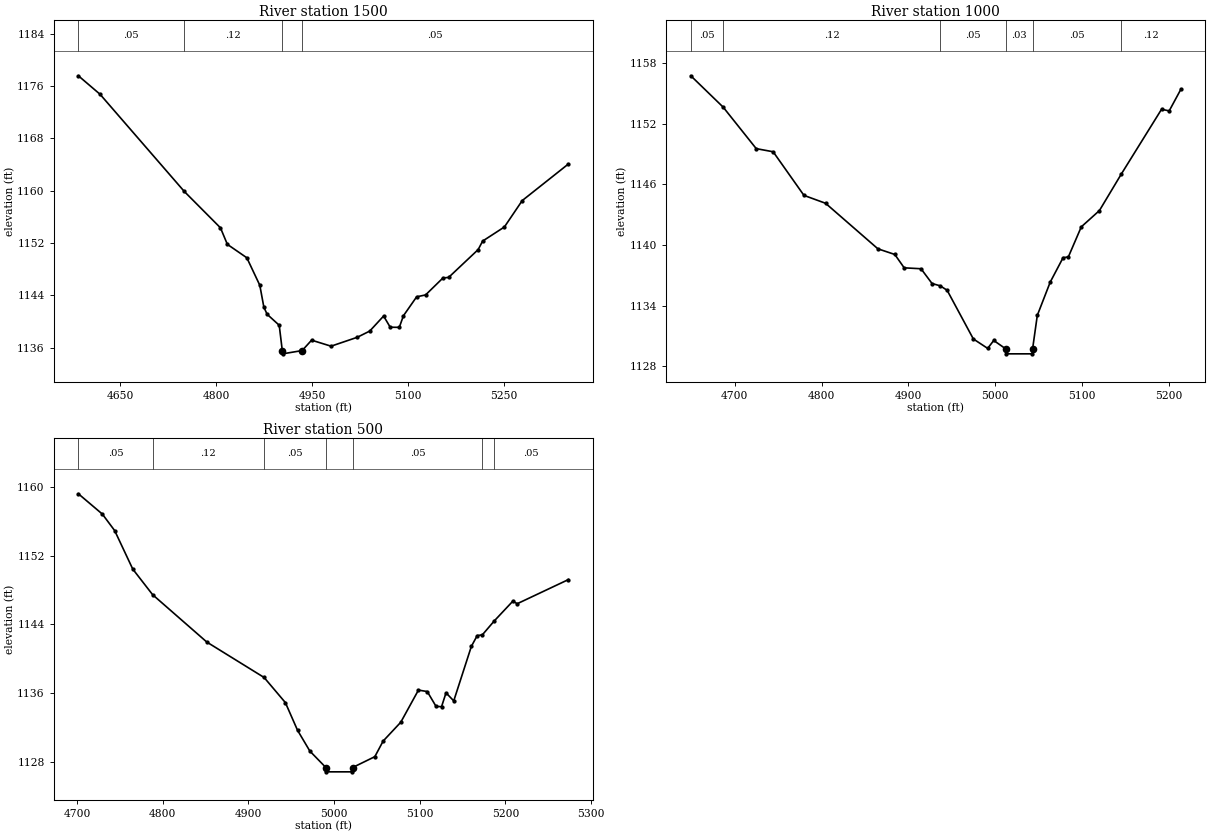
Type RM Length L Ch R = 1 ,1500    ,500,500,500
BEGIN DESCRIPTION:
BABYHEAD CREEK 3.0
END DESCRIPTION:
XS GIS Cut Line= 3
      2805355.73     10276103.11      2804945.82     10276167.26
      2804605.68     10276253.11
#Sta/Elev= 30
  4585.1 1177.56    4619 1174.73  4750.6 1159.87  4807.1 1154.31  4817.9 1151.78
  4848.3 1149.73  4868.6 1145.52  4874.9 1142.18    4880 1141.09  4898.9 1139.41
  4903.7 1135.54  4904.2 1135.04  4934.7 1135.54  4949.5 1137.13  4979.9 1136.21
  5020.8 1137.57  5040.3 1138.52    5062 1140.82  5072.3 1139.11  5086.5 1139.09
    5093 1140.87  5113.6 1143.76  5127.6 1144.05  5154.8 1146.65  5163.5 1146.72
  5209.7 1150.98  5216.7 1152.28  5250.7 1154.44  5278.6 1158.48  5350.8 1164.08
#Mann= 4 ,-1 , 0
  4585.1     .05       0  4750.6     .12       0  4903.7     .05       0
  4934.7     .05       0
Bank Sta=4903.7,4934.7
XS Rating Curve= 0 ,0
Exp/Cntr=0.3,0.1

Type RM Length L Ch R = 1 ,1000    ,500,500,500
BEGIN DESCRIPTION:
BABYHEAD CREEK 2.0
END DESCRIPTION:
XS GIS Cut Line= 3
      2804755.69     10275453.11      2804631.65     10275781.14
      2804455.69     10275903.11
#Sta/Elev= 30
  4649.3 1156.73  4686.6 1153.63  4724.7 1149.53  4744.2 1149.22  4779.7 1144.91
  4804.6 1144.13  4864.9 1139.63  4884.4 1139.07  4895.2 1137.75  4914.6 1137.66
  4927.3  1136.2  4936.8 1135.97  4944.7 1135.53  4974.9 1130.72  4991.4 1129.79
  4998.4 1130.57  5012.1 1129.75  5012.6 1129.25  5042.7 1129.25  5043.2 1129.75
  5048.6 1133.05  5063.5 1136.34  5078.3 1138.75  5084.4 1138.83  5099.3  1141.8
  5120.2 1143.41  5145.5 1147.03  5191.8 1153.42  5200.6 1153.26  5214.1  1155.4
#Mann= 6 ,-1 , 0
  4649.3     .05       0  4686.6     .12       0  4936.8     .05       0
  5012.1     .03       0  5043.2     .05       0  5145.5     .12       0
Bank Sta=5012.1,5043.2
XS Rating Curve= 0 ,0
Exp/Cntr=0.3,0.1

Type RM Length L Ch R = 1 ,500     ,0,0,0
BEGIN DESCRIPTION:
BABYHEAD CREEK 1.0
END DESCRIPTION:
XS GIS Cut Line= 3
      2804505.65     10275253.14      2804270.92     10275437.55
      2804205.67     10275703.15
#Sta/Elev= 30
  4701.5 1159.25  4729.5 1156.88  4743.9 1154.95    4765 1150.46  4788.2 1147.47
  4851.5 1141.94  4918.3 1137.81  4943.1 1134.88  4957.3 1131.65  4971.7 1129.22
  4990.4  1127.3  4990.9  1126.8    5021  1126.8  5021.5  1127.3  5047.5 1128.57
  5057.2 1130.39  5077.8 1132.59  5098.4 1136.34  5108.7 1136.17    5119 1134.43
  5125.4 1134.41  5130.6 1136.02  5139.6 1135.08  5160.2 1141.45    5167  1142.7
    5173 1142.79  5186.8  1144.4  5208.6 1146.72  5213.7 1146.42  5273.5 1149.24
#Mann= 7 ,-1 , 0
  4701.5     .05       0  4788.2     .12       0  4918.3     .05       0
  4990.4     .03       0  5021.5     .05       0    5173     .12       0
  5186.8     .05       0
Bank Sta=4990.4,5021.5
XS Rating Curve= 0 ,0
Exp/Cntr=0.3,0.1

Chan Stop Cuts=-1
Use User Specified Reach Order=0
Composite Channel Slope=5