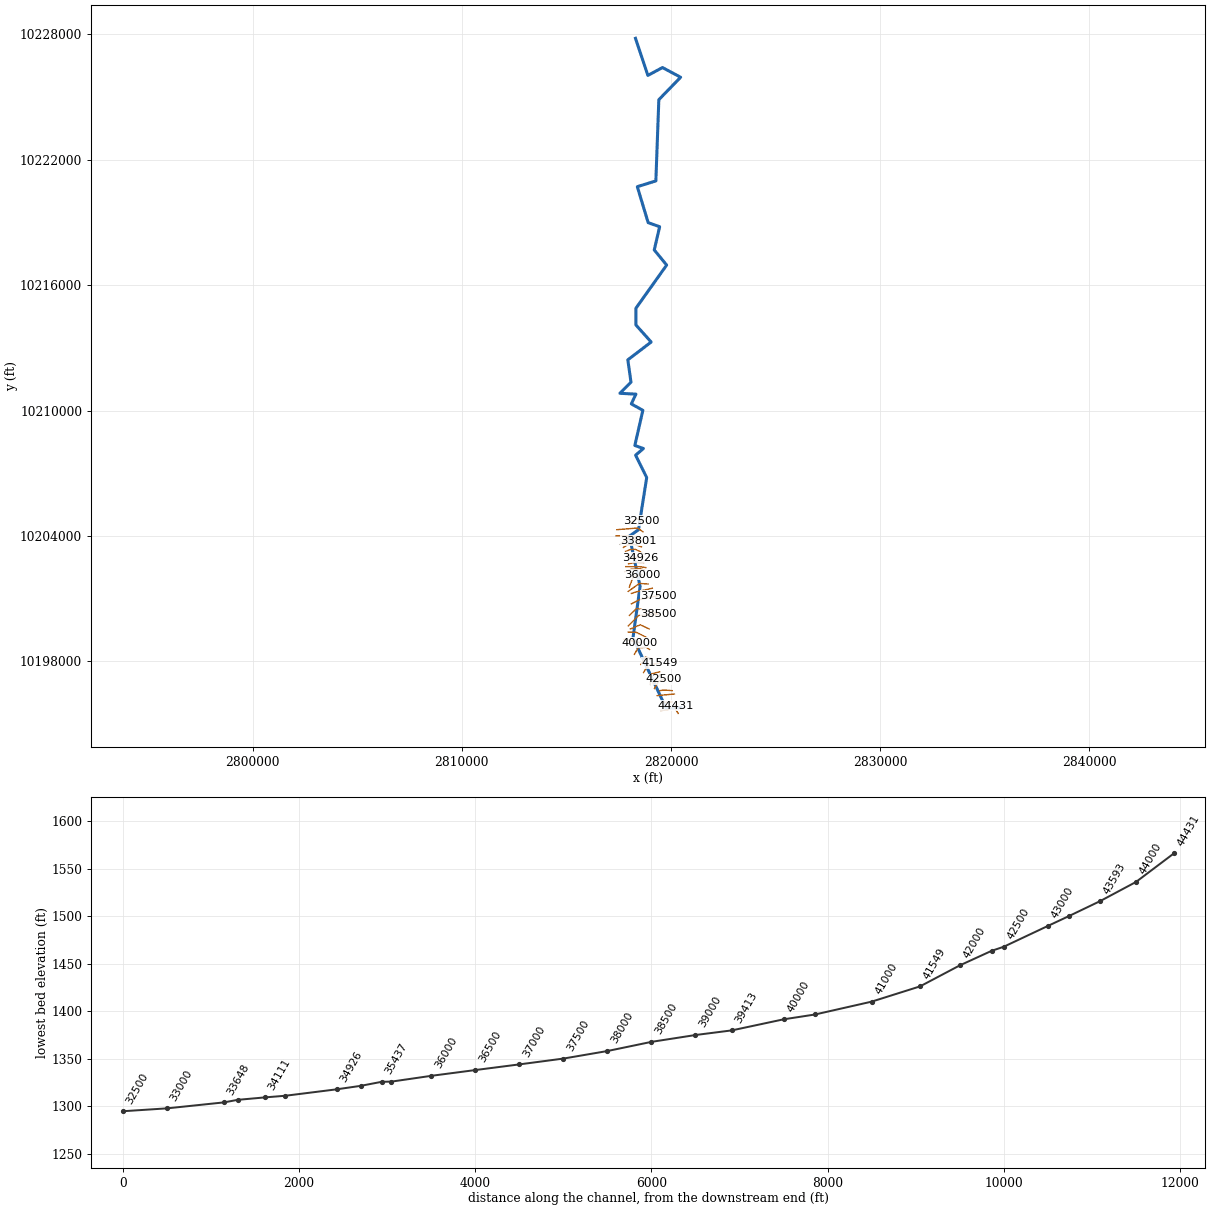
--- BAILEY BRANCH.prj (project) ---

Proj Title=BAILEY BRANCH Base Level Engineering
Current Plan=p01
Default Exp/Contr=0.3,0.1
English Units
Geom File=g01
Flow File=f01
Plan File=p01
BEGIN DESCRIPTION:
BAILEY BRANCH
END DESCRIPTION:

--- BAILEY BRANCH.p01 (plan) ---

Plan Title=Multiple Run
Short Identifier=Multiple
Geom File=g01
Flow File=f01
Subcritical Flow
K Sum by GR= 0
Std Step Tol= 0.01
Critical Tol= 0.01
Num of Std Step Trials= 20
Max Error Tol= 0.3
Flow Tol Ratio= 0.001
Split Flow NTrial= 30
Split Flow Tol= 0.02
Split Flow Ratio= 0.02
Log Output Level= 0
Friction Slope Method= 1
Unsteady Friction Slope Method= 2
Unsteady Bridges Friction Slope Method= 1
Parabolic Critical Depth
Global Vel Dist=  1 , 1 , 1
Global Log Level= 0
CheckData=True
Encroach Param= -1, 0, 0, 0
BEGIN DESCRIPTION:
Multiple Run
END DESCRIPTION:

--- BAILEY BRANCH.f01 (steady flow) ---

Flow Title=Multiple
Number of Profiles=7
Profile Names=10-year,25-year,50-year,1pct_min,100-year,1pct_plu,500-year
River Rch & RM= BAILEY BRANCH,Reach-1,44431
     498     819    1782    1370    2547    4734    3767
River Rch & RM= BAILEY BRANCH,Reach-1,31942
     741    1241    2934    1864    4257    9726    6257
River Rch & RM= BAILEY BRANCH,Reach-1,30223
     935    1595    3597    2359    5232   11605    7646
River Rch & RM= BAILEY BRANCH,Reach-1,26000
    1168    2024    4426    2703    6462   15449    9400
River Rch & RM= BAILEY BRANCH,Reach-1,21000
    1525    2705    5685    4843    8359   14429   12157
River Rch & RM= BAILEY BRANCH,Reach-1,11000
    1647    2936    6156    4469    9068   18398   13168
River Rch & RM= BAILEY BRANCH,Reach-1,9000
    2332    4244    8962    6565   13320   27022   19206
Boundary for River Rch & Prof#=BAILEY BRANCH,Reach-1,1
Up Type=0
Dn Type=3
Dn Slope=0.005
Boundary for River Rch & Prof#=BAILEY BRANCH,Reach-1,2
Up Type=0
Dn Type=3
Dn Slope=0.005
Boundary for River Rch & Prof#=BAILEY BRANCH,Reach-1,3
Up Type=0
Dn Type=3
Dn Slope=0.005
Boundary for River Rch & Prof#=BAILEY BRANCH,Reach-1,4
Up Type=0
Dn Type=3
Dn Slope=0.005
Boundary for River Rch & Prof#=BAILEY BRANCH,Reach-1,5
Up Type=0
Dn Type=3
Dn Slope=0.005
Boundary for River Rch & Prof#=BAILEY BRANCH,Reach-1,6
Up Type=0
Dn Type=3
Dn Slope=0.005
Boundary for River Rch & Prof#=BAILEY BRANCH,Reach-1,7
Up Type=0
Dn Type=3
Dn Slope=0.005

--- BAILEY BRANCH.g01 (geometry) ---

Geom Title=Existing Conditions

River Reach=BAILEY BRANCH,Reach-1
Reach XY= 30
      2820469.00     10195788.00      2819767.25     10195759.00
      2818181.75     10199133.00      2818519.50     10201585.00
      2818009.50     10203997.00      2818443.50     10204300.00
      2818836.00     10206796.00      2818305.75     10207867.00
      2818678.75     10208186.00      2818269.75     10208333.00
      2818652.50     10210012.00      2818100.50     10210323.00
      2818321.50     10210788.00      2817555.50     10210828.00
      2818084.25     10211360.00      2817934.75     10212429.00
      2819049.75     10213281.00      2818318.00     10214100.00
      2818317.75     10214893.00      2819790.00     10216962.00
      2819198.00     10217688.00      2819455.25     10218796.00
      2818906.25     10218993.00      2818387.50     10220713.00
      2819274.00     10220988.00      2819416.50     10224875.00
      2820458.50     10225948.00      2819590.00     10226412.00
      2818892.75     10226036.00      2818300.75     10227810.00

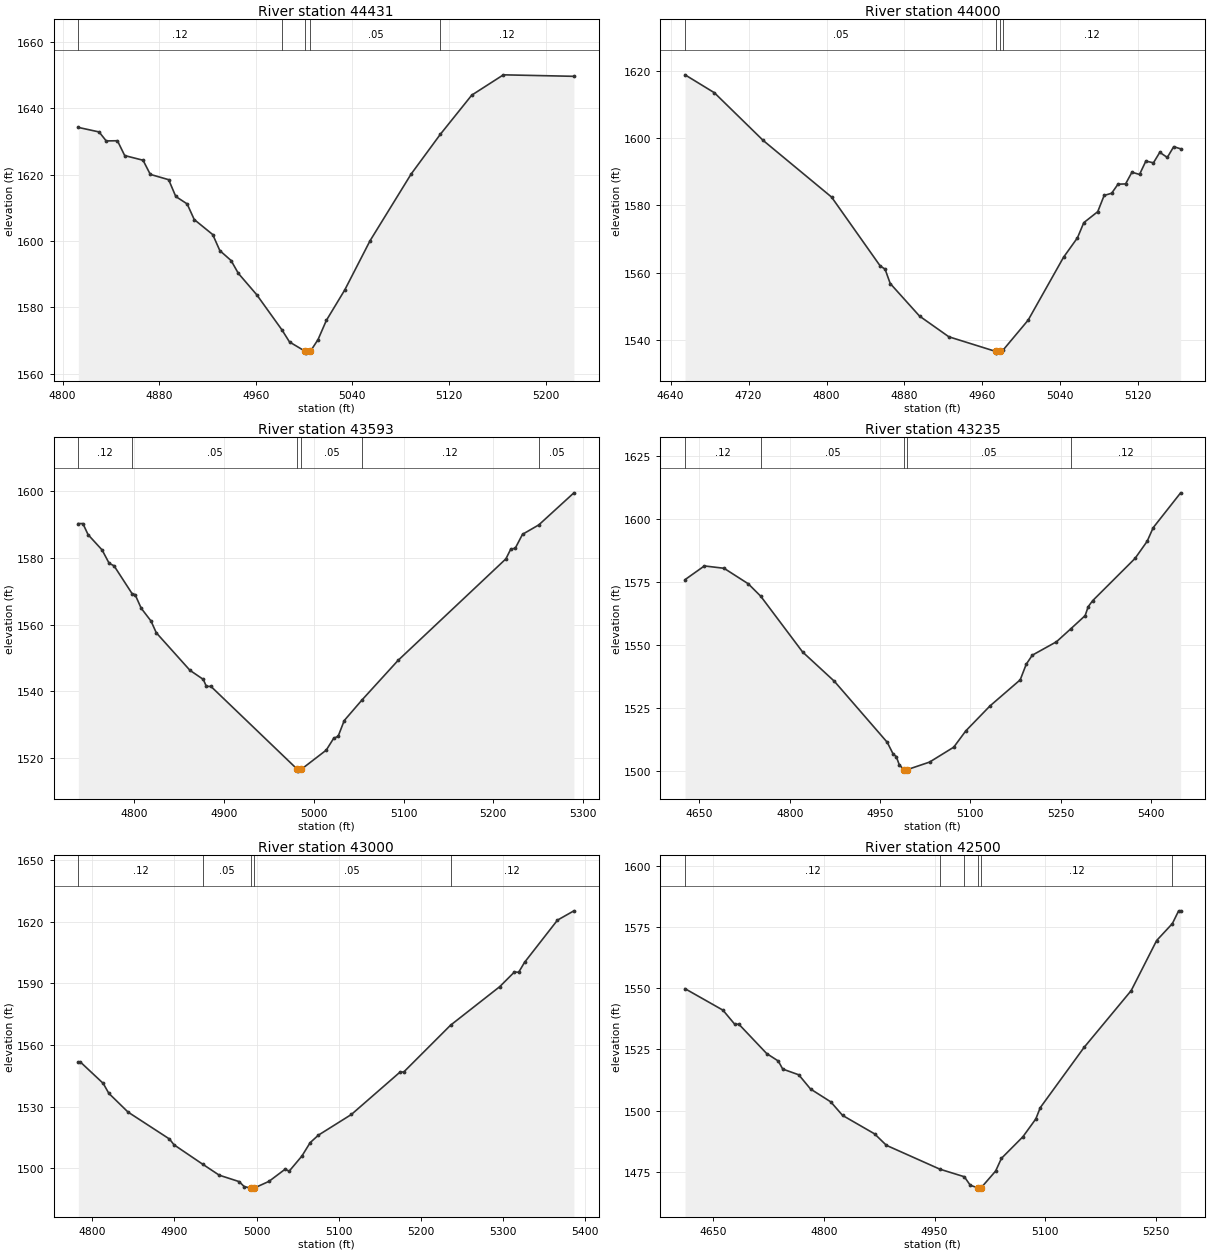
Type RM Length L Ch R = 1,44431,431,431,431
BEGIN DESCRIPTION:
Mapping XS 7ea3c0a1
END DESCRIPTION:
XS GIS Cut Line= 3
      2820340.99     10195515.36      2820210.95     10195720.84
      2820195.34     10195887.34
#Sta/Elev= 30
  4813.1 1634.23  4830.3 1632.86  4836.2 1630.16  4845.5 1630.21  4851.5 1625.75
  4866.7 1624.34  4872.7 1620.08  4887.9 1618.48  4893.8 1613.42  4903.2 1611.19
  4909.1 1606.47  4924.4 1601.95  4930.3 1597.11  4939.6 1594.13  4945.6 1590.27
  4960.8 1583.84  4981.8 1573.19  4988.0 1569.59  5001.2 1566.73  5001.4 1566.23
  5005.2 1566.73  5011.6 1570.31  5018.5 1576.09  5033.7 1585.24  5054.7 1600.10
  5088.7 1620.18  5112.9 1632.16  5138.9 1643.95  5165.1 1650.07  5223.5 1649.62
#Mann=5,-1,0
  4813.1    0.12       0  4981.8    0.05       0  5001.2    0.05       0
  5005.2    0.05       0  5112.9    0.12       0
Bank Sta=5001.2,5005.2
Exp/Cntr=0.3,0.1

Type RM Length L Ch R = 1,44000,407,407,407
BEGIN DESCRIPTION:
BAILEY BRANCH 87.0
END DESCRIPTION:
XS GIS Cut Line= 3
      2819505.66     10195653.11      2819849.93     10195678.36
      2819955.66     10195803.08
#Sta/Elev= 30
  4654.8 1618.77  4684.9 1613.45  4735.0 1599.28  4805.2 1582.46  4855.1 1562.01
  4860.1 1561.06  4865.4 1556.79  4895.5 1547.11  4925.6 1540.96  4973.7 1536.61
  4973.9 1536.11  4977.7 1536.61  4981.4 1537.07  5007.0 1545.92  5043.3 1564.58
  5057.6 1570.37  5064.1 1574.86  5078.4 1578.12  5085.0 1582.95  5092.7 1583.60
  5099.2 1586.29  5107.0 1586.37  5113.5 1589.85  5121.3 1589.18  5127.8 1593.15
  5135.6 1592.64  5142.1 1595.75  5149.8 1594.23  5156.4 1597.43  5163.5 1596.79
#Mann=4,-1,0
  4654.8    0.05       0  4973.7    0.07       0  4977.7    0.05       0
  4981.4    0.12       0
Bank Sta=4973.7,4977.7
Exp/Cntr=0.3,0.1

Type RM Length L Ch R = 1,43593,358,358,358
BEGIN DESCRIPTION:
Mapping XS 5b134ef8
END DESCRIPTION:
XS GIS Cut Line= 4
      2819511.34     10195983.53      2819643.96     10196040.74
      2819997.68     10196058.95      2820051.46     10196058.95
#Sta/Elev= 30
  4737.5 1590.35  4742.6 1590.35  4748.4 1587.01  4764.0 1582.42  4771.9 1578.39
  4777.3 1577.67  4797.5 1569.26  4800.8 1569.00  4807.6 1564.90  4818.5 1561.07
  4824.4 1557.53  4862.0 1546.23  4876.8 1543.52  4880.2 1541.42  4885.3 1541.42
  4981.8 1516.45  4982.0 1515.95  4985.8 1516.45  5013.8 1522.25  5022.1 1525.80
  5027.1 1526.42  5033.9 1531.15  5053.5 1537.28  5093.9 1549.23  5214.1 1579.75
  5219.5 1582.67  5224.5 1582.93  5232.6 1587.12  5250.8 1589.96  5289.9 1599.59
#Mann=6,-1,0
  4737.5    0.12       0  4797.5    0.05       0  4981.8    0.05       0
  4985.8    0.05       0  5053.5    0.12       0  5250.8    0.05       0
Bank Sta=4981.8,4985.8
Exp/Cntr=0.3,0.1

Type RM Length L Ch R = 1,43235,235,235,235
BEGIN DESCRIPTION:
Mapping XS 51cd7a28
END DESCRIPTION:
XS GIS Cut Line= 2
      2819341.20     10196364.83      2820161.09     10196442.92
#Sta/Elev= 30
  4626.0 1575.93  4658.1 1581.36  4690.8 1580.43  4731.0 1574.29  4751.7 1569.38
  4821.4 1547.24  4874.1 1535.65  4962.0 1511.45  4972.0 1506.72  4977.0 1505.80
  4982.1 1502.49  4990.1 1500.52  4990.4 1500.02  4994.1 1500.52  5032.3 1503.60
  5072.5 1509.51  5092.6 1515.98  5132.8 1525.87  5183.0 1536.21  5193.0 1542.39
  5203.1 1545.98  5243.3 1551.31  5267.3 1556.49  5290.9 1561.67  5296.0 1565.22
  5303.5 1567.61  5373.9 1584.36  5393.9 1591.11  5404.0 1596.53  5449.6 1610.34
#Mann=5,-1,0
  4626.0    0.12       0  4751.7    0.05       0  4990.1    0.05       0
  4994.1    0.05       0  5267.3    0.12       0
Bank Sta=4990.1,4994.1
Exp/Cntr=0.3,0.1

Type RM Length L Ch R = 1,43000,500,500,500
BEGIN DESCRIPTION:
BAILEY BRANCH 85.0
END DESCRIPTION:
XS GIS Cut Line= 3
      2819455.66     10196603.11      2819670.67     10196630.94
      2820055.67     10196603.11
#Sta/Elev= 30
  4783.2 1551.71  4785.7 1551.71  4813.5 1541.29  4820.3 1536.46  4843.7 1527.32
  4894.1 1514.20  4899.6 1511.39  4934.7 1501.88  4954.6 1496.60  4978.9 1493.46
  4984.9 1491.06  4993.0 1490.31  4993.2 1489.81  4997.0 1490.31  5015.1 1493.59
  5034.7 1499.50  5039.7 1498.56  5055.2 1505.95  5065.2 1512.45  5075.2 1516.09
  5115.3 1526.15  5174.2 1546.69  5179.2 1546.91  5235.9 1569.61  5295.8 1588.40
  5313.7 1595.56  5318.8 1595.40  5325.9 1600.20  5366.0 1620.79  5386.0 1625.32
#Mann=5,-1,0
  4783.2    0.12       0  4934.7    0.05       0  4993.0    0.05       0
  4997.0    0.05       0  5235.9    0.12       0
Bank Sta=4993,4997
Exp/Cntr=0.3,0.1

Type RM Length L Ch R = 1,42500,139,139,139
BEGIN DESCRIPTION:
BAILEY BRANCH 84.0
END DESCRIPTION:
XS GIS Cut Line= 3
      2819205.70     10196703.15      2819395.79     10197041.05
      2819655.66     10197153.10
#Sta/Elev= 30
  4612.3 1549.73  4663.6 1540.97  4679.5 1535.24  4685.2 1535.22  4722.8 1523.26
  4738.5 1520.21  4744.5 1516.93  4766.2 1514.59  4782.1 1508.80  4809.5 1503.55
  4825.5 1498.02  4868.8 1490.49  4884.8 1485.81  4957.2 1476.07  4990.3 1472.98
  4998.3 1469.51  5008.8 1468.43  5009.0 1467.93  5012.8 1468.43  5032.6 1475.30
  5040.5 1480.50  5069.5 1489.29  5087.0 1496.58  5093.0 1501.17  5152.3 1525.76
  5216.1 1548.96  5250.5 1569.38  5271.8 1576.30  5280.3 1581.51  5283.0 1581.51
#Mann=6,-1,0
  4612.3    0.12       0  4957.2    0.05       0  4990.3    0.12       0
  5008.8    0.07       0  5012.8    0.12       0  5271.8    0.05       0
Bank Sta=5008.8,5012.8
Exp/Cntr=0.3,0.1

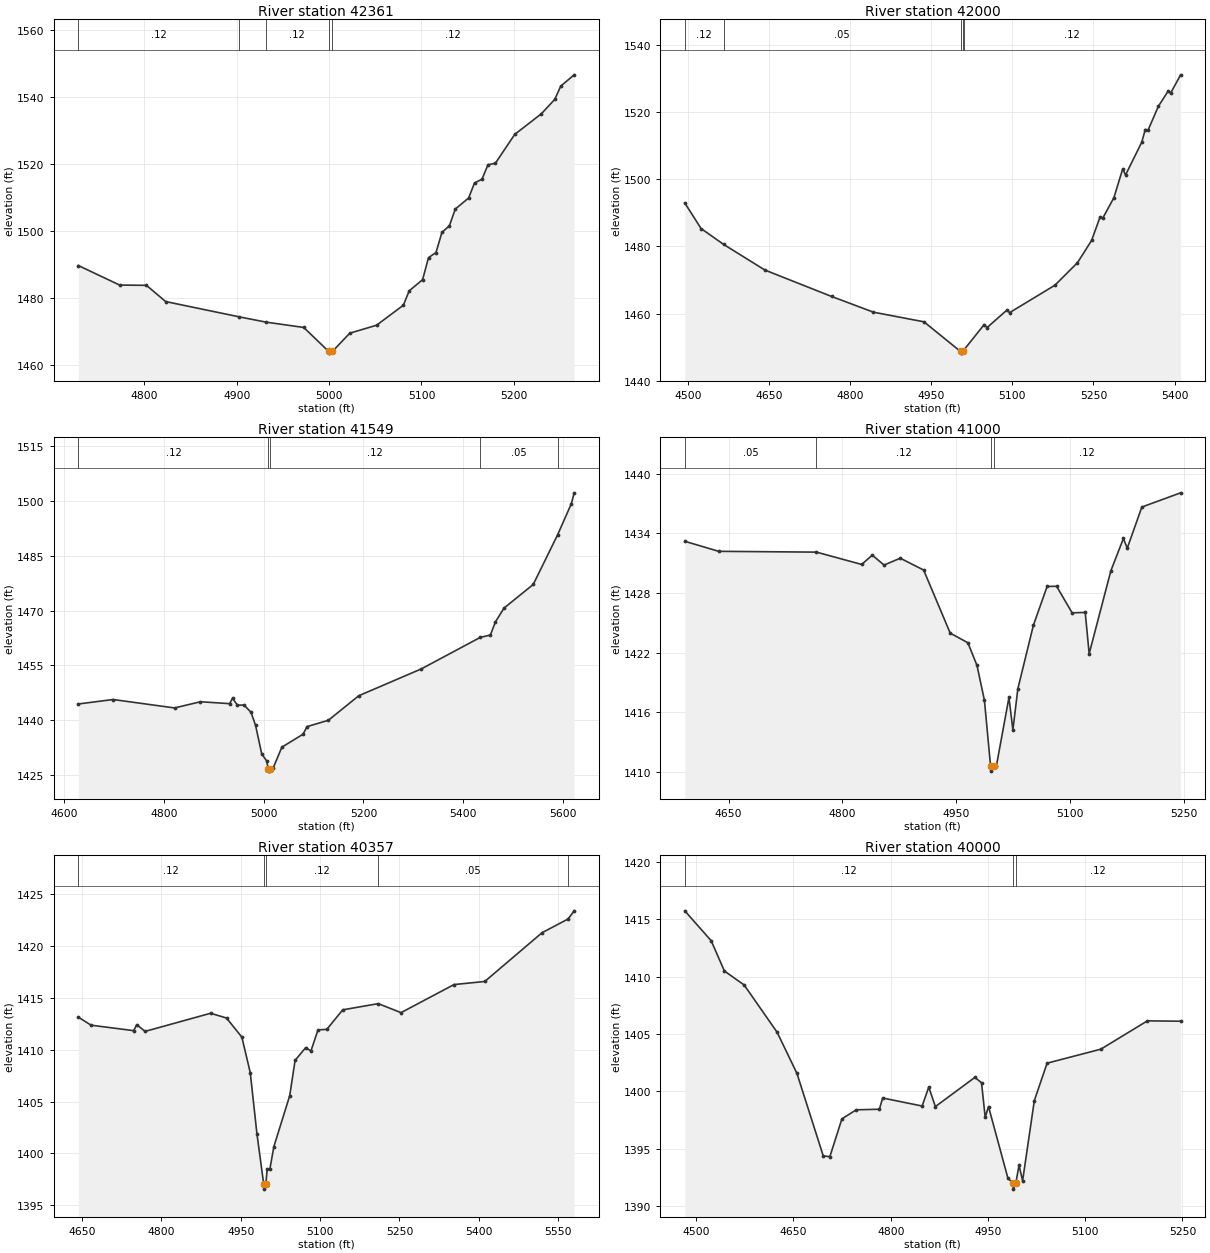
Type RM Length L Ch R = 1,42361,361,361,361
BEGIN DESCRIPTION:
Mapping XS 320ef403
END DESCRIPTION:
XS GIS Cut Line= 2
      2819142.42     10196933.94      2819470.46     10197358.46
#Sta/Elev= 30
  4728.7 1489.76  4773.4 1483.92  4802.4 1483.84  4823.2 1478.99  4903.0 1474.41
  4931.5 1472.86  4972.6 1471.25  4999.6 1464.08  4999.9 1463.58  5003.6 1464.08
  5022.4 1469.54  5051.4 1471.92  5080.4 1477.90  5086.7 1482.19  5101.2 1485.54
  5107.6 1492.11  5115.7 1493.65  5122.1 1499.63  5130.2 1501.65  5136.6 1506.64
  5151.0 1509.94  5157.4 1514.45  5165.5 1515.56  5171.9 1519.86  5180.0 1520.34
  5200.9 1528.95  5229.8 1535.13  5244.3 1539.45  5250.7 1543.38  5265.2 1546.75
#Mann=5,-1,0
  4728.7    0.12       0  4903.0    0.05       0  4931.5    0.12       0
  4999.6    0.07       0  5003.6    0.12       0
Bank Sta=4999.6,5003.6
Exp/Cntr=0.3,0.1

Type RM Length L Ch R = 1,42000,451,451,451
BEGIN DESCRIPTION:
BAILEY BRANCH 83.0
END DESCRIPTION:
XS GIS Cut Line= 3
      2819005.69     10196903.16      2819056.09     10197406.34
      2819455.64     10197503.10
#Sta/Elev= 30
  4494.3 1492.93  4524.4 1485.32  4566.2 1480.59  4642.4 1472.97  4765.6 1465.12
  4843.2 1460.43  4936.5 1457.57  5004.1 1448.75  5004.4 1448.25  5008.1 1448.75
  5010.3 1449.18  5047.9 1456.76  5053.1 1455.83  5089.8 1461.05  5094.9 1460.30
  5178.6 1468.45  5220.4 1475.16  5246.5 1481.78  5262.2 1488.78  5267.3 1488.47
  5287.7 1494.49  5304.0 1503.06  5309.2 1501.25  5339.1 1510.96  5345.8 1514.79
  5351.0 1514.64  5370.0 1521.71  5387.7 1526.14  5392.8 1525.66  5411.1 1531.06
#Mann=5,-1,0
  4494.3    0.12       0  4566.2    0.05       0  5004.1    0.05       0
  5008.1    0.05       0  5010.3    0.12       0
Bank Sta=5004.1,5008.1
Exp/Cntr=0.3,0.1

Type RM Length L Ch R = 1,41549,549,549,549
BEGIN DESCRIPTION:
Mapping XS 6a1bcd8d
END DESCRIPTION:
XS GIS Cut Line= 3
      2818685.82     10197467.07      2818894.17     10197818.66
      2819471.06     10197922.76
#Sta/Elev= 30
  4627.9 1444.49  4697.6 1445.71  4820.9 1443.41  4873.0 1445.10  4931.5 1444.58
  4937.3 1446.05  4947.1 1444.17  4960.4 1444.19  4974.4 1442.23  4983.6 1438.62
  4995.8 1430.91  5005.6 1428.97  5009.4 1426.66  5009.7 1426.16  5013.4 1426.66
  5018.5 1426.90  5036.3 1432.70  5078.8 1436.24  5086.8 1438.31  5129.6 1440.04
  5190.5 1446.73  5316.3 1454.08  5434.3 1462.66  5454.7 1463.31  5464.9 1466.92
  5482.1 1470.67  5540.7 1477.12  5589.6 1490.67  5617.3 1499.21  5622.8 1502.13
#Mann=5,-1,0
  4627.9    0.12       0  5009.4    0.07       0  5013.4    0.12       0
  5434.3    0.05       0  5589.6    0.12       0
Bank Sta=5009.4,5013.4
Exp/Cntr=0.3,0.1

Type RM Length L Ch R = 1,41000,643,643,643
BEGIN DESCRIPTION:
BAILEY BRANCH 81.0
END DESCRIPTION:
XS GIS Cut Line= 3
      2818555.68     10197853.11      2818765.09     10198202.80
      2819005.71     10198153.11
#Sta/Elev= 30
  4592.4 1433.19  4637.1 1432.18  4765.9 1432.10  4825.5 1430.86  4839.4 1431.80
  4854.9 1430.80  4876.3 1431.49  4907.1 1430.30  4942.1 1423.96  4965.4 1422.99
  4977.4 1420.71  4987.2 1417.20  4995.3 1410.59  4995.5 1410.09  4999.3 1410.59
  5002.9 1410.59  5019.5 1417.49  5024.7 1414.22  5031.2 1418.36  5051.7 1424.75
  5069.8 1428.65  5082.3 1428.67  5102.7 1426.00  5120.0 1426.04  5125.2 1421.89
  5153.8 1430.23  5170.3 1433.47  5175.4 1432.50  5194.6 1436.63  5245.7 1438.06
#Mann=4,-1,0
  4592.4    0.05       0  4765.9    0.12       0  4995.3    0.07       0
  4999.3    0.12       0
Bank Sta=4995.3,4999.3
Exp/Cntr=0.3,0.1

Type RM Length L Ch R = 1,40357,357,357,357
BEGIN DESCRIPTION:
Mapping XS b8f9f54a
END DESCRIPTION:
XS GIS Cut Line= 4
      2818247.49     10198339.53      2818425.42     10198652.00
      2818816.05     10198678.04      2818971.50     10198574.40
#Sta/Elev= 30
  4642.7 1413.16  4666.7 1412.38  4747.4 1411.85  4753.2 1412.43  4769.0 1411.78
  4892.9 1413.53  4923.0 1413.07  4952.0 1411.23  4967.9 1407.80  4980.5 1401.92
  4993.3 1397.05  4993.5 1396.55  4997.3 1397.05  5000.0 1398.46  5004.9 1398.46
  5012.6 1400.66  5042.6 1405.58  5052.7 1408.98  5072.7 1410.21  5082.7 1409.89
  5096.0 1411.92  5112.8 1411.98  5142.8 1413.86  5210.0 1414.46  5253.1 1413.59
  5353.3 1416.30  5411.5 1416.60  5519.7 1421.30  5569.0 1422.63  5580.6 1423.42
#Mann=5,-1,0
  4642.7    0.12       0  4993.3    0.07       0  4997.3    0.12       0
  5210.0    0.05       0  5569.0    0.12       0
Bank Sta=4993.3,4997.3
Exp/Cntr=0.3,0.1

Type RM Length L Ch R = 1,40000,587,587,587
BEGIN DESCRIPTION:
BAILEY BRANCH 79.0
END DESCRIPTION:
XS GIS Cut Line= 3
      2817755.65     10199053.12      2818264.60     10198958.29
      2818505.66     10198903.12
#Sta/Elev= 30
  4482.3 1415.74  4523.0 1413.13  4543.4 1410.49  4573.9 1409.27  4624.7 1405.15
  4655.3 1401.56  4695.9 1394.36  4706.1 1394.29  4724.7 1397.59  4746.8 1398.38
  4782.5 1398.43  4787.6 1399.41  4848.5 1398.71  4858.7 1400.36  4868.9 1398.66
  4929.9 1401.21  4940.1 1400.74  4945.8 1397.73  4950.9 1398.66  4980.8 1392.42
  4988.9 1391.96  4989.2 1391.46  4992.9 1391.96  4998.0 1393.54  5003.5 1392.19
  5021.6 1399.19  5041.3 1402.45  5124.2 1403.67  5196.0 1406.14  5247.3 1406.11
#Mann=3,-1,0
  4482.3    0.12       0  4988.9    0.07       0  4992.9    0.12       0
Bank Sta=4988.9,4992.9
Exp/Cntr=0.3,0.1

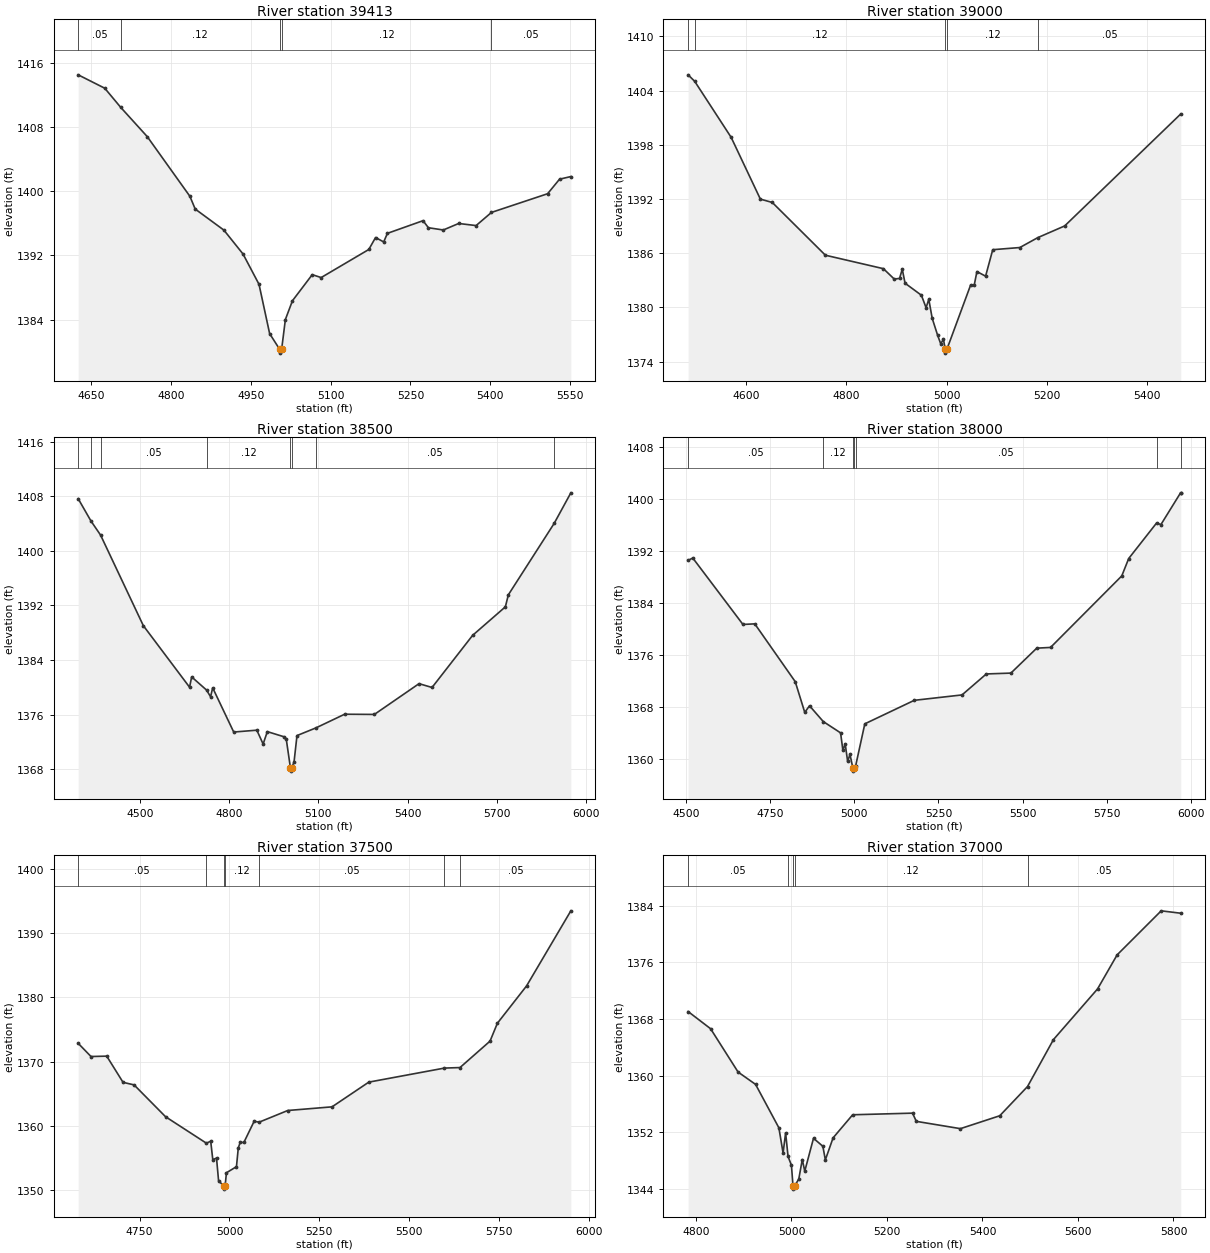
Type RM Length L Ch R = 1,39413,413,413,413
BEGIN DESCRIPTION:
BAILEY BRANCH 78.0
END DESCRIPTION:
XS GIS Cut Line= 3
      2817955.66     10199403.11      2818330.50     10199396.25
      2818824.75     10199151.12
#Sta/Elev= 30
  4625.1 1414.51  4675.1 1412.84  4704.9 1410.47  4755.1 1406.80  4835.2 1399.37
  4845.2 1397.78  4899.2 1395.15  4935.2 1392.17  4965.2 1388.40  4985.2 1382.25
  5003.8 1380.32  5004.0 1379.82  5007.8 1380.32  5014.8 1384.01  5028.1 1386.35
  5065.3 1389.60  5082.1 1389.24  5171.7 1392.74  5184.4 1394.23  5199.7 1393.68
  5206.7 1394.75  5273.7 1396.33  5283.8 1395.45  5311.8 1395.17  5340.7 1395.98
  5373.5 1395.72  5402.4 1397.36  5508.0 1399.69  5530.4 1401.50  5551.7 1401.83
#Mann=5,-1,0
  4625.1    0.05       0  4704.9    0.12       0  5003.8    0.07       0
  5007.8    0.12       0  5402.4    0.05       0
Bank Sta=5003.8,5007.8
Exp/Cntr=0.3,0.1

Type RM Length L Ch R = 1,39000,500,500,500
BEGIN DESCRIPTION:
BAILEY BRANCH 77.0
END DESCRIPTION:
XS GIS Cut Line= 3
      2818055.70     10199553.12      2818532.04     10199752.28
      2818955.66     10199553.12
#Sta/Elev= 30
  4483.7 1405.74  4496.9 1405.02  4569.7 1398.82  4628.1 1391.98  4651.9 1391.61
  4758.0 1385.77  4873.9 1384.28  4895.6 1383.13  4906.2 1383.20  4911.6 1384.22
  4917.2 1382.67  4949.8 1381.34  4959.2 1379.96  4964.6 1380.89  4971.4 1378.79
  4982.3 1376.90  4988.4 1375.97  4993.9 1376.45  4997.3 1375.43  4997.5 1374.93
  5001.3 1375.43  5048.2 1382.47  5055.3 1382.44  5060.8 1383.96  5078.1 1383.45
  5092.4 1386.38  5146.5 1386.62  5182.5 1387.72  5236.1 1389.01  5468.1 1401.41
#Mann=5,-1,0
  4483.7    0.05       0  4496.9    0.12       0  4997.3    0.07       0
  5001.3    0.12       0  5182.5    0.05       0
Bank Sta=4997.3,5001.3
Exp/Cntr=0.3,0.1

Type RM Length L Ch R = 1,38500,500,500,500
BEGIN DESCRIPTION:
BAILEY BRANCH 76.0
END DESCRIPTION:
XS GIS Cut Line= 3
      2817955.72     10199703.14      2818457.56     10200202.42
      2819405.70     10200253.11
#Sta/Elev= 30
  4292.1 1407.65  4335.4 1404.36  4367.4 1402.32  4511.3 1389.04  4666.8 1380.02
  4673.9 1381.53  4724.0 1379.60  4737.5 1378.62  4744.6 1379.93  4815.3 1373.45
  4893.1 1373.72  4914.3 1371.69  4928.4 1373.51  4985.0 1372.75  4992.1 1372.41
  5006.1 1368.22  5006.4 1367.72  5010.1 1368.22  5018.2 1369.02  5028.2 1372.93
  5092.1 1374.06  5188.4 1376.06  5288.5 1376.03  5438.8 1380.54  5482.5 1379.98
  5619.0 1387.62  5729.2 1391.80  5739.2 1393.56  5893.2 1404.02  5949.5 1408.51
#Mann=8,-1,0
  4292.1    0.05       0  4335.4    0.12       0  4367.4    0.05       0
  4724.0    0.12       0  5006.1    0.07       0  5010.1    0.12       0
  5092.1    0.05       0  5893.2    0.12       0
Bank Sta=5006.1,5010.1
Exp/Cntr=0.3,0.1

Type RM Length L Ch R = 1,38000,500,500,500
BEGIN DESCRIPTION:
BAILEY BRANCH 75.0
END DESCRIPTION:
XS GIS Cut Line= 3
      2818005.66     10200203.09      2818365.35     10200541.26
      2819305.67     10200303.12
#Sta/Elev= 30
  4506.3 1390.52  4520.3 1390.87  4669.2 1380.65  4704.4 1380.74  4824.6 1371.84
  4852.9 1367.11  4867.0 1368.13  4907.9 1365.70  4959.3 1363.96  4966.2 1361.27
  4973.0 1362.26  4980.3 1359.56  4987.2 1360.65  4995.7 1358.57  4996.0 1358.07
  4999.7 1358.57  5003.8 1358.82  5031.3 1365.35  5178.3 1368.97  5320.1 1369.80
  5392.3 1373.03  5465.3 1373.16  5542.1 1377.00  5583.1 1377.11  5794.7 1388.12
  5815.3 1390.80  5897.9 1396.25  5911.1 1396.03  5969.4 1400.91  5970.0 1400.91
#Mann=7,-1,0
  4506.3    0.05       0  4907.9    0.12       0  4995.7    0.07       0
  4999.7    0.12       0  5003.8    0.05       0  5897.9    0.12       0
  5969.4    0.05       0
Bank Sta=4995.7,4999.7
Exp/Cntr=0.3,0.1

Type RM Length L Ch R = 1,37500,500,500,500
BEGIN DESCRIPTION:
BAILEY BRANCH 74.0
END DESCRIPTION:
XS GIS Cut Line= 3
      2818105.71     10200753.12      2818476.49     10200952.96
      2819405.67     10201153.11
#Sta/Elev= 30
  4578.8 1372.84  4614.5 1370.78  4658.3 1370.84  4703.7 1366.76  4734.5 1366.36
  4822.1 1361.40  4935.7 1357.28  4947.8 1357.58  4953.6 1354.71  4964.0 1354.96
  4969.7 1351.42  4983.9 1350.62  4984.2 1350.12  4987.9 1350.62  4991.6 1352.67
  5019.5 1353.62  5024.6 1356.55  5029.9 1357.40  5040.1 1357.39  5068.8 1360.70
  5082.5 1360.55  5162.3 1362.37  5285.6 1362.94  5387.9 1366.79  5598.6 1368.98
  5641.8 1369.06  5725.5 1373.18  5745.9 1375.96  5827.2 1381.78  5950.5 1393.48
#Mann=7,-1,0
  4578.8    0.05       0  4935.7    0.12       0  4983.9    0.07       0
  4987.9    0.12       0  5082.5    0.05       0  5598.6    0.12       0
  5641.8    0.05       0
Bank Sta=4983.9,4987.9
Exp/Cntr=0.3,0.1

Type RM Length L Ch R = 1,37000,500,500,500
BEGIN DESCRIPTION:
BAILEY BRANCH 73.0
END DESCRIPTION:
XS GIS Cut Line= 3
      2818105.68     10201253.11      2818310.63     10201322.59
      2819105.69     10201503.11
#Sta/Elev= 30
  4783.6 1369.07  4830.7 1366.64  4888.3 1360.52  4924.9 1358.78  4973.7 1352.65
  4982.5 1349.08  4987.8 1351.94  4992.9 1348.60  5000.0 1347.36  5003.2 1344.49
  5003.4 1343.99  5007.2 1344.49  5015.4 1345.42  5022.7 1348.17  5027.9 1346.53
  5046.2 1351.17  5065.8 1350.04  5071.0 1348.12  5087.2 1351.23  5128.2 1354.49
  5253.6 1354.72  5261.5 1353.56  5353.8 1352.53  5436.2 1354.35  5494.4 1358.48
  5548.7 1365.11  5641.0 1372.26  5682.0 1377.07  5774.3 1383.29  5815.3 1382.95
#Mann=5,-1,0
  4783.6    0.05       0  4992.9    0.12       0  5003.2    0.07       0
  5007.2    0.12       0  5494.4    0.05       0
Bank Sta=5003.2,5007.2
Exp/Cntr=0.3,0.1

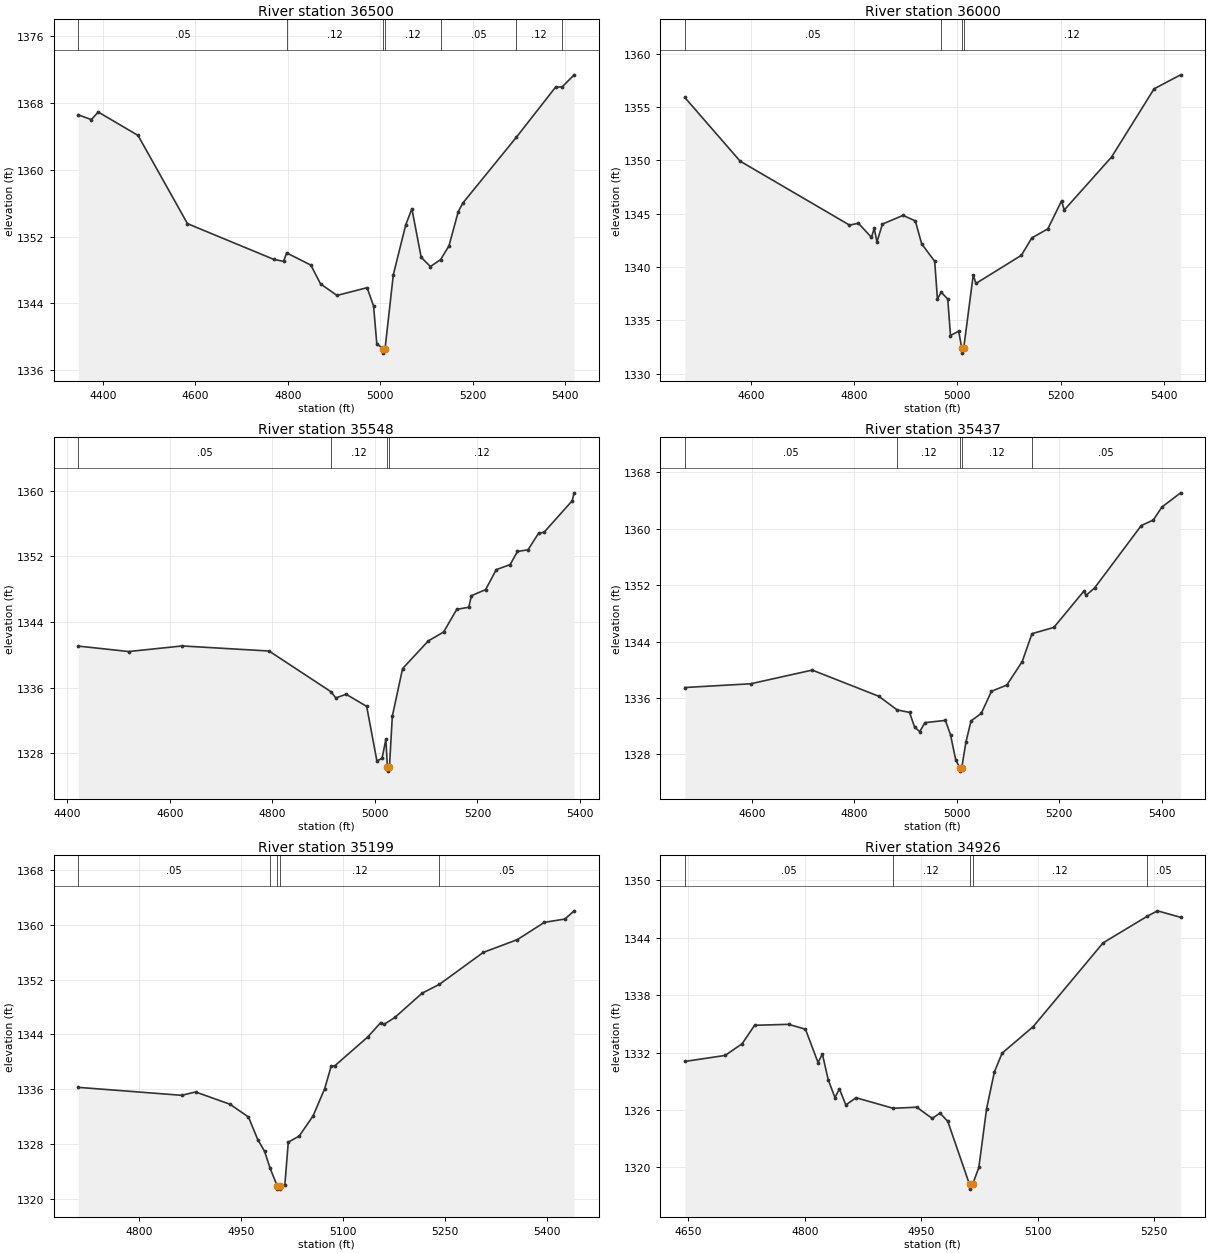
Type RM Length L Ch R = 1,36500,500,500,500
BEGIN DESCRIPTION:
BAILEY BRANCH 72.0
END DESCRIPTION:
XS GIS Cut Line= 3
      2817955.70     10201353.13      2818487.41     10201732.02
      2818905.72     10201703.11
#Sta/Elev= 30
  4347.1 1366.60  4375.3 1366.03  4390.1 1366.94  4476.2 1364.13  4583.1 1353.55
  4770.0 1349.26  4790.9 1349.03  4797.6 1350.04  4849.9 1348.58  4870.8 1346.33
  4906.4 1344.94  4971.6 1345.87  4985.6 1343.66  4992.5 1339.14  5006.3 1338.52
  5006.5 1338.02  5010.3 1338.52  5028.3 1347.44  5055.1 1353.41  5068.4 1355.33
  5088.5 1349.51  5108.5 1348.41  5130.5 1349.24  5148.6 1350.89  5168.7 1355.00
  5178.7 1356.03  5294.0 1363.89  5379.2 1369.93  5393.3 1369.95  5419.3 1371.40
#Mann=7,-1,0
  4347.1    0.05       0  4797.6    0.12       0  5006.3    0.07       0
  5010.3    0.12       0  5130.5    0.05       0  5294.0    0.12       0
  5393.3    0.05       0
Bank Sta=5006.3,5010.3
Exp/Cntr=0.3,0.1

Type RM Length L Ch R = 1,36000,452,452,452
BEGIN DESCRIPTION:
BAILEY BRANCH 71.0
END DESCRIPTION:
XS GIS Cut Line= 3
      2818005.67     10201553.08      2818185.52     10202049.51
      2818605.64     10202153.10
#Sta/Elev= 30
  4472.0 1355.90  4579.2 1349.93  4791.1 1343.94  4808.4 1344.11  4833.7 1342.79
  4839.0 1343.64  4844.3 1342.36  4854.9 1344.03  4894.9 1344.85  4918.7 1344.33
  4930.9 1342.19  4956.2 1340.54  4961.5 1337.02  4968.9 1337.64  4981.5 1337.01
  4986.8 1333.59  5002.7 1334.00  5008.5 1332.44  5008.7 1331.94  5012.5 1332.44
  5030.9 1339.27  5036.1 1338.47  5124.2 1341.11  5144.4 1342.74  5175.3 1343.58
  5202.0 1346.21  5207.2 1345.35  5298.9 1350.32  5381.3 1356.71  5432.7 1358.02
#Mann=4,-1,0
  4472.0    0.05       0  4968.9    0.12       0  5008.5    0.07       0
  5012.5    0.12       0
Bank Sta=5008.5,5012.5
Exp/Cntr=0.3,0.1

Type RM Length L Ch R = 1,35548,111,111,111
BEGIN DESCRIPTION:
Mapping XS 40eede2b
END DESCRIPTION:
XS GIS Cut Line= 4
      2817786.10     10202294.01      2818102.84     10202415.23
      2818501.67     10202434.78      2818722.60     10202376.65
#Sta/Elev= 30
  4421.6 1341.07  4519.9 1340.41  4624.1 1341.09  4793.6 1340.47  4914.4 1335.51
  4923.8 1334.76  4943.8 1335.21  4983.9 1333.73  5003.9 1327.07  5013.9 1327.42
  5021.3 1329.71  5024.3 1326.35  5024.6 1325.85  5028.3 1326.35  5033.9 1332.53
  5053.9 1338.33  5104.0 1341.70  5134.0 1342.79  5159.6 1345.55  5183.0 1345.80
  5188.2 1347.21  5215.9 1347.95  5236.6 1350.38  5263.6 1350.99  5277.9 1352.59
  5298.6 1352.80  5319.3 1354.83  5329.7 1354.92  5384.6 1358.76  5388.5 1359.73
#Mann=4,-1,0
  4421.6    0.05       0  4914.4    0.12       0  5024.3    0.07       0
  5028.3    0.12       0
Bank Sta=5024.3,5028.3
Exp/Cntr=0.3,0.1

Type RM Length L Ch R = 1,35437,238,238,238
BEGIN DESCRIPTION:
Mapping XS 053f4b55
END DESCRIPTION:
XS GIS Cut Line= 4
      2817836.95     10202536.45      2818192.77     10202532.54
      2818525.13     10202532.54      2818801.73     10202489.68
#Sta/Elev= 30
  4469.0 1337.49  4597.7 1338.02  4717.8 1339.96  4847.8 1336.25  4883.6 1334.32
  4907.8 1333.96  4917.8 1331.86  4927.8 1331.24  4937.8 1332.51  4977.8 1332.83
  4987.8 1330.80  4997.8 1327.28  5005.8 1326.14  5006.0 1325.64  5009.8 1326.14
  5017.8 1329.71  5027.8 1332.75  5047.8 1333.82  5067.8 1336.96  5097.8 1337.84
  5127.8 1341.17  5146.9 1345.12  5189.6 1346.01  5247.6 1351.10  5252.7 1350.57
  5269.1 1351.60  5360.2 1360.44  5383.8 1361.23  5400.6 1363.07  5437.1 1365.08
#Mann=5,-1,0
  4469.0    0.05       0  4883.6    0.12       0  5005.8    0.07       0
  5009.8    0.12       0  5146.9    0.05       0
Bank Sta=5005.8,5009.8
Exp/Cntr=0.3,0.1

Type RM Length L Ch R = 1,35199,273,273,273
BEGIN DESCRIPTION:
Mapping XS 5e7ec243
END DESCRIPTION:
XS GIS Cut Line= 3
      2817965.93     10202673.29      2818333.53     10202739.77
      2818689.38     10202731.95
#Sta/Elev= 30
  4710.2 1336.25  4862.4 1335.09  4882.7 1335.58  4933.5 1333.78  4960.5 1331.92
  4974.2 1328.63  4984.3 1326.90  4992.1 1324.50  5002.7 1321.89  5002.9 1321.39
  5006.4 1321.39  5006.7 1321.89  5014.0 1321.97  5019.1 1328.25  5035.1 1329.13
  5055.5 1332.07  5072.6 1336.04  5082.3 1339.38  5087.3 1339.38  5135.9 1343.60
  5155.2 1345.72  5160.2 1345.47  5175.9 1346.46  5215.9 1350.00  5241.5 1351.30
  5306.0 1355.96  5356.0 1357.82  5396.0 1360.35  5426.0 1360.83  5439.7 1362.03
#Mann=5,-1,0
  4710.2    0.05       0  4992.1    0.12       0  5002.7    0.07       0
  5006.7    0.12       0  5241.5    0.05       0
Bank Sta=5002.7,5006.7
Exp/Cntr=0.3,0.1

Type RM Length L Ch R = 1,34926,581,581,581
BEGIN DESCRIPTION:
Mapping XS cc0b00cf
END DESCRIPTION:
XS GIS Cut Line= 3
      2817903.57     10203082.16      2818094.53     10202978.00
      2818515.52     10202969.32
#Sta/Elev= 30
  4645.5 1331.07  4697.4 1331.70  4719.3 1332.92  4735.4 1334.85  4779.1 1334.95
  4800.9 1334.44  4817.1 1330.96  4822.7 1331.84  4830.2 1329.17  4838.9 1327.29
  4844.6 1328.21  4852.9 1326.53  4866.1 1327.28  4913.7 1326.18  4944.2 1326.29
  4964.2 1325.12  4974.2 1325.68  4984.2 1324.81  5012.2 1318.23  5012.5 1317.73
  5016.2 1318.23  5024.2 1319.99  5034.2 1326.13  5044.2 1329.97  5054.2 1331.94
  5094.2 1334.71  5184.2 1343.46  5240.8 1346.23  5254.3 1346.81  5284.1 1346.13
#Mann=5,-1,0
  4645.5    0.05       0  4913.7    0.12       0  5012.2    0.07       0
  5016.2    0.12       0  5240.8    0.05       0
Bank Sta=5012.2,5016.2
Exp/Cntr=0.3,0.1

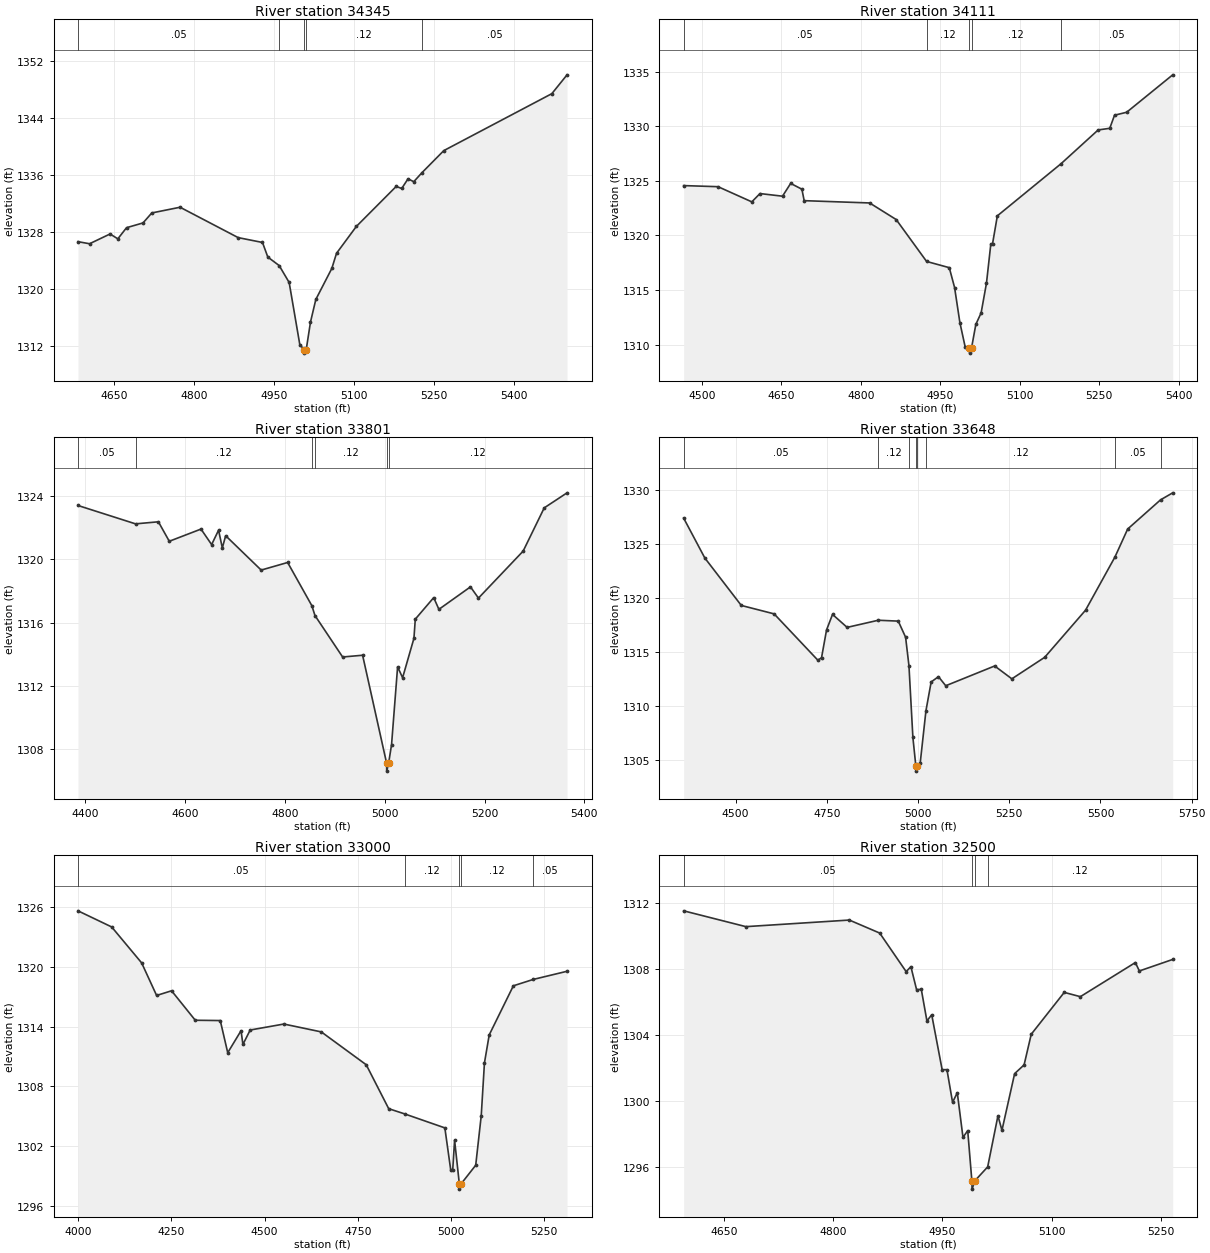
Type RM Length L Ch R = 1,34345,234,234,234
BEGIN DESCRIPTION:
Mapping XS c66ef250
END DESCRIPTION:
XS GIS Cut Line= 5
      2817825.25     10203267.65      2818079.37     10203357.57
      2818298.34     10203361.48      2818509.49     10203259.82
      2818661.34     10203139.11
#Sta/Elev= 30
  4582.5 1326.60  4604.2 1326.31  4642.6 1327.68  4657.2 1327.00  4673.5 1328.56
  4704.4 1329.23  4720.9 1330.63  4773.9 1331.43  4882.8 1327.17  4928.4 1326.49
  4938.4 1324.44  4959.7 1323.25  4978.4 1320.88  4998.4 1312.15  5006.4 1311.47
  5006.7 1310.97  5010.4 1311.47  5018.4 1315.33  5028.4 1318.50  5058.4 1322.85
  5067.2 1324.97  5104.4 1328.74  5179.1 1334.35  5189.4 1334.06  5201.3 1335.42
  5212.0 1335.01  5227.3 1336.27  5268.3 1339.37  5470.9 1347.36  5499.4 1350.00
#Mann=5,-1,0
  4582.5    0.05       0  4959.7    0.12       0  5006.4    0.07       0
  5010.4    0.12       0  5227.3    0.05       0
Bank Sta=5006.4,5010.4
Exp/Cntr=0.3,0.1

Type RM Length L Ch R = 1,34111,310,310,310
BEGIN DESCRIPTION:
Mapping XS ccb7cfd4
END DESCRIPTION:
XS GIS Cut Line= 4
      2817719.62     10203451.40      2817915.15     10203572.63
      2818267.06     10203596.09      2818587.65     10203482.71
#Sta/Elev= 30
  4465.8 1324.57  4530.7 1324.47  4594.4 1323.08  4609.8 1323.84  4652.3 1323.60
  4667.7 1324.77  4688.9 1324.24  4693.2 1323.19  4816.7 1322.98  4866.8 1321.46
  4924.2 1317.62  4967.0 1317.05  4977.0 1315.23  4987.0 1312.02  4997.1 1309.76
  5005.1 1309.72  5005.3 1309.22  5009.1 1309.72  5017.1 1311.85  5027.1 1312.91
  5037.2 1315.64  5045.4 1319.23  5048.6 1319.23  5057.7 1321.80  5178.0 1326.58
  5247.9 1329.67  5269.8 1329.82  5278.8 1331.02  5301.7 1331.29  5388.6 1334.72
#Mann=5,-1,0
  4465.8    0.05       0  4924.2    0.12       0  5005.1    0.07       0
  5009.1    0.12       0  5178.0    0.05       0
Bank Sta=5005.1,5009.1
Exp/Cntr=0.3,0.1

Type RM Length L Ch R = 1,33801,153,153,153
BEGIN DESCRIPTION:
Mapping XS 2f74d083
END DESCRIPTION:
XS GIS Cut Line= 4
      2817574.93     10203596.06      2817872.14     10203858.07
      2818145.85     10203869.80      2818439.12     10203772.04
#Sta/Elev= 30
  4386.0 1323.41  4501.2 1322.25  4547.0 1322.38  4568.8 1321.15  4632.3 1321.92
  4653.6 1320.94  4667.5 1321.85  4675.0 1320.73  4681.7 1321.50  4752.8 1319.33
  4805.8 1319.81  4854.3 1317.08  4860.5 1316.46  4915.9 1313.84  4955.9 1313.95
  5004.0 1307.13  5004.2 1306.63  5008.0 1307.13  5013.9 1308.31  5026.0 1313.22
  5036.0 1312.53  5058.7 1315.02  5061.4 1316.23  5098.3 1317.59  5108.7 1316.85
  5171.9 1318.27  5187.9 1317.56  5277.4 1320.53  5319.6 1323.26  5365.3 1324.21
#Mann=6,-1,0
  4386.0    0.05       0  4501.2    0.12       0  4854.3    0.05       0
  4860.5    0.12       0  5004.0    0.07       0  5008.0    0.12       0
Bank Sta=5004,5008
Exp/Cntr=0.3,0.1

Type RM Length L Ch R = 1,33648,648,648,648
BEGIN DESCRIPTION:
Mapping XS 223a7063
END DESCRIPTION:
XS GIS Cut Line= 5
      2817367.69     10204010.56      2817711.82     10204010.56
      2818153.67     10203987.10      2818513.40     10203936.27
      2818579.54     10203757.30
#Sta/Elev= 30
  4357.4 1327.39  4415.4 1323.70  4515.4 1319.31  4605.4 1318.53  4725.4 1314.24
  4735.4 1314.48  4749.1 1317.04  4765.5 1318.48  4805.5 1317.28  4890.9 1317.94
  4945.7 1317.86  4965.8 1316.37  4975.0 1313.74  4985.8 1307.10  4993.8 1304.48
  4994.1 1303.98  4997.8 1304.48  5005.8 1304.71  5021.6 1309.57  5035.9 1312.23
  5055.9 1312.72  5075.9 1311.88  5210.0 1313.71  5257.1 1312.52  5347.1 1314.51
  5459.1 1318.87  5539.7 1323.79  5574.6 1326.38  5664.7 1329.08  5698.1 1329.73
#Mann=8,-1,0
  4357.4    0.05       0  4890.9    0.12       0  4975.0    0.05       0
  4993.8    0.03       0  4997.8    0.05       0  5021.6    0.12       0
  5539.7    0.05       0  5664.7    0.12       0
Bank Sta=4993.8,4997.8
Exp/Cntr=0.3,0.1

Type RM Length L Ch R = 1,33000,500,500,500
BEGIN DESCRIPTION:
BAILEY BRANCH 65.0
END DESCRIPTION:
XS GIS Cut Line= 3
      2817405.64     10204303.11      2818402.34     10204383.09
      2818655.71     10204203.09
#Sta/Elev= 30
  4000.1 1325.63  4090.4 1324.01  4170.7 1320.40  4210.8 1317.13  4250.9 1317.60
  4314.4 1314.64  4381.4 1314.61  4401.4 1311.38  4437.1 1313.59  4442.1 1312.21
  4461.6 1313.66  4551.9 1314.26  4652.2 1313.47  4772.6 1310.17  4832.8 1305.76
  4875.2 1305.24  4983.3 1303.83  4999.2 1299.56  5004.3 1299.56  5009.4 1302.59
  5022.2 1298.18  5022.4 1297.68  5026.2 1298.18  5066.0 1300.08  5080.8 1305.05
  5089.4 1310.35  5102.2 1313.17  5166.9 1318.10  5220.2 1318.74  5310.8 1319.56
#Mann=5,-1,0
  4000.1    0.05       0  4875.2    0.12       0  5022.2    0.07       0
  5026.2    0.12       0  5220.2    0.05       0
Bank Sta=5022.2,5026.2
Exp/Cntr=0.3,0.1

Type RM Length L Ch R = 1,32500,558,558,558
BEGIN DESCRIPTION:
BAILEY BRANCH 64.0
END DESCRIPTION:
XS GIS Cut Line= 3
      2818030.65     10204578.08      2818339.23     10204840.38
      2818580.71     10204728.10
#Sta/Elev= 30
  4595.0 1311.54  4680.4 1310.58  4822.4 1310.98  4864.1 1310.19  4900.4 1307.85
  4906.9 1308.15  4914.7 1306.76  4921.2 1306.77  4928.9 1304.86  4935.5 1305.23
  4949.8 1301.90  4956.4 1301.90  4964.1 1299.92  4970.6 1300.50  4978.4 1297.79
  4984.9 1298.20  4990.6 1295.15  4990.9 1294.65  4994.6 1295.15  5012.3 1296.00
  5026.4 1299.10  5031.9 1298.22  5049.3 1301.66  5062.3 1302.19  5072.1 1304.05
  5117.4 1306.59  5139.5 1306.33  5215.0 1308.40  5220.5 1307.89  5266.3 1308.59
#Mann=4,-1,0
  4595.0    0.05       0  4990.6    0.03       0  4994.6    0.05       0
  5012.3    0.12       0
Bank Sta=4990.6,4994.6
Exp/Cntr=0.3,0.1