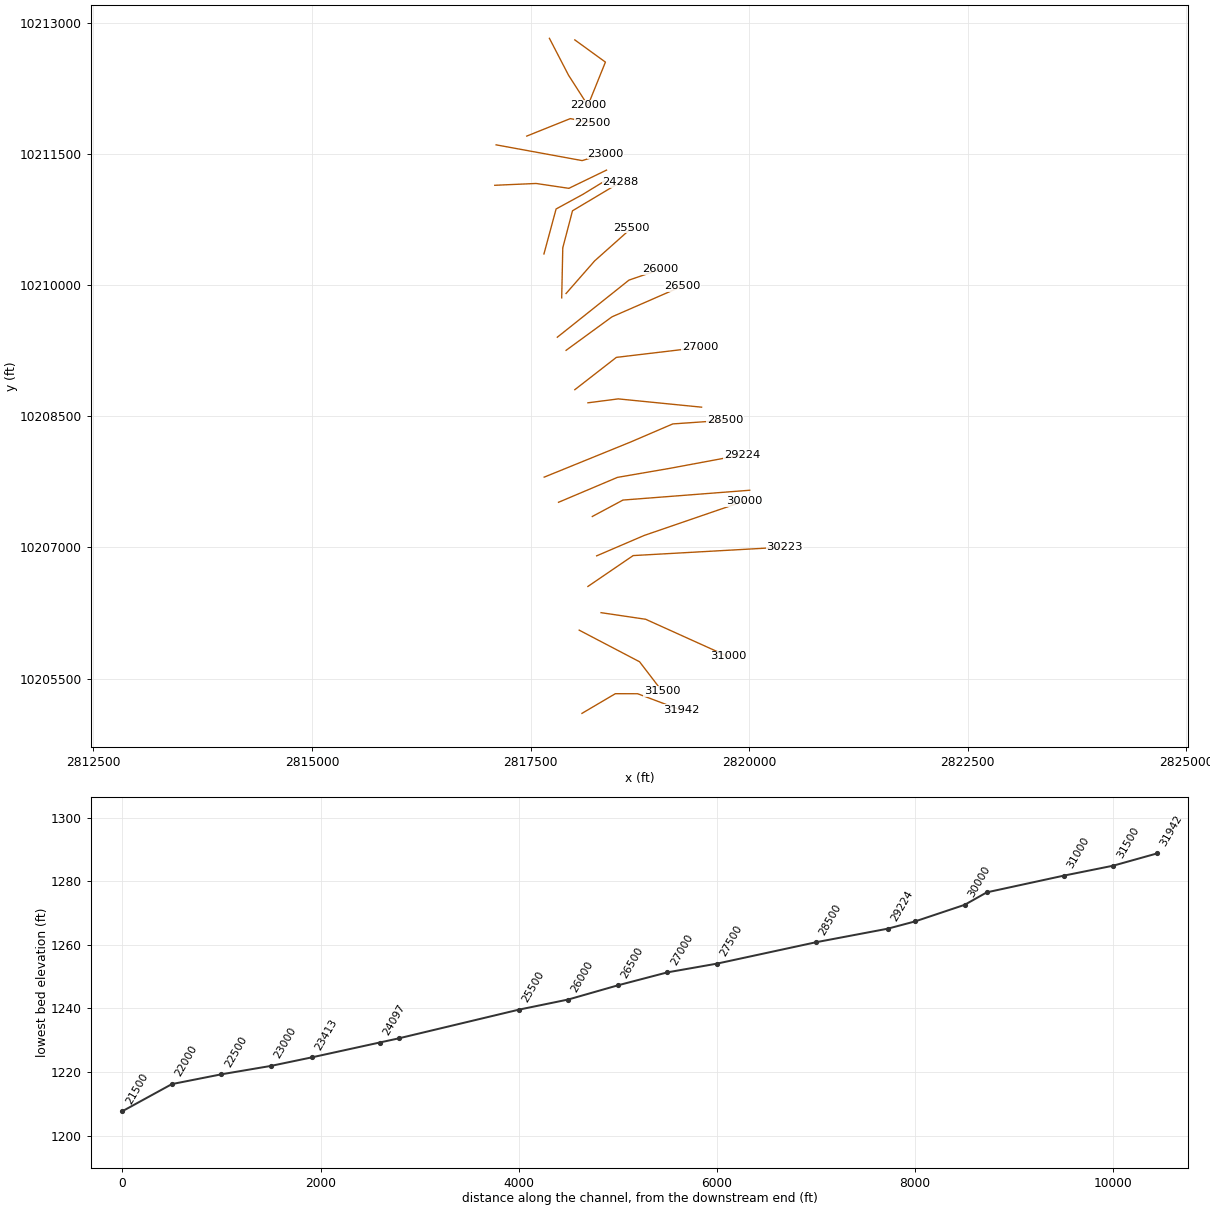
HEC-RAS study BAILEY BRANCH.prj: BAILEY BRANCH Base Level Engineering

--- BAILEY BRANCH.g01 (geometry) --- (continued)

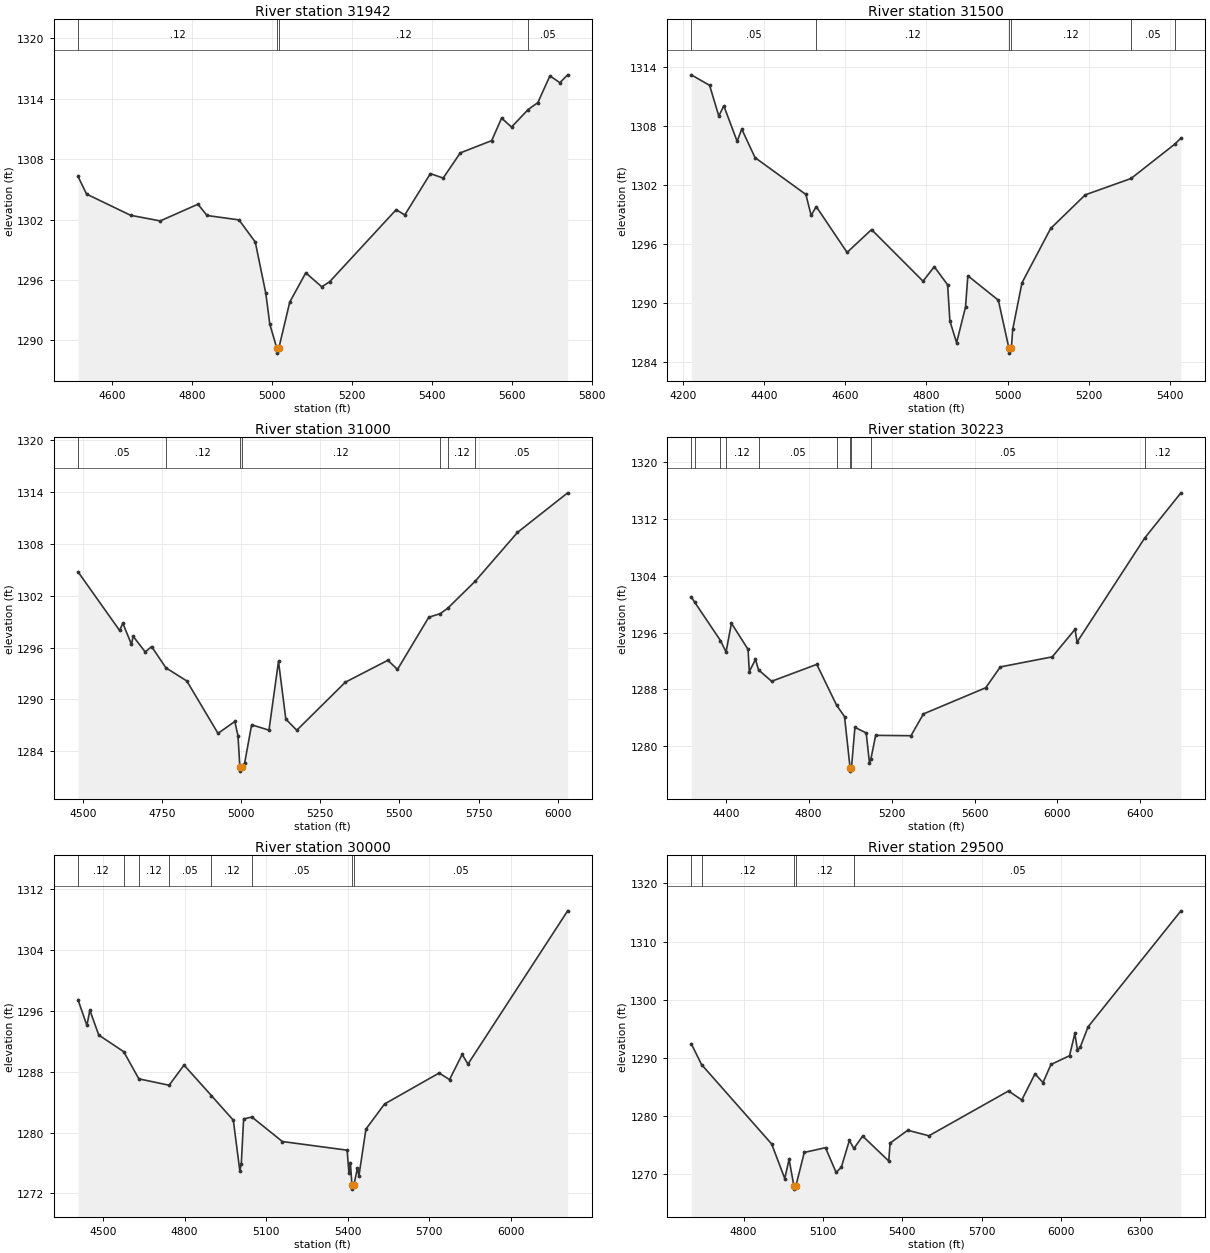
Type RM Length L Ch R = 1,31942,442,442,442
BEGIN DESCRIPTION:
BAILEY BRANCH 63.0
END DESCRIPTION:
XS GIS Cut Line= 4
      2818087.22     10205101.50      2818469.30     10205326.65
      2818724.94     10205325.89      2819217.20     10205140.59
#Sta/Elev= 30
  4514.0 1306.28  4535.4 1304.53  4645.5 1302.42  4719.7 1301.86  4814.0 1303.52
  4836.8 1302.40  4916.8 1301.96  4957.5 1299.76  4983.9 1294.65  4993.9 1291.59
  5011.3 1289.22  5011.7 1288.72  5016.4 1289.22  5043.9 1293.81  5083.9 1296.70
  5123.9 1295.31  5143.9 1295.83  5310.1 1302.98  5331.5 1302.45  5395.6 1306.56
  5427.6 1306.12  5470.4 1308.62  5549.0 1309.84  5573.8 1312.08  5598.6 1311.19
  5640.3 1312.93  5664.5 1313.62  5694.7 1316.28  5719.6 1315.60  5739.1 1316.38
#Mann=4,-1,0
  4514.0    0.12       0  5011.3    0.07       0  5016.4    0.12       0
  5640.3    0.05       0
Bank Sta=5011.3,5016.4
Exp/Cntr=0.3,0.1

Type RM Length L Ch R = 1,31500,500,500,500
BEGIN DESCRIPTION:
BAILEY BRANCH 62.0
END DESCRIPTION:
XS GIS Cut Line= 3
      2818055.70     10206053.10      2818745.98     10205691.84
      2819005.67     10205353.14
#Sta/Elev= 30
  4220.9 1313.25  4266.0 1312.18  4288.6 1309.05  4301.0 1310.09  4333.8 1306.47
  4345.1 1307.72  4377.9 1304.81  4503.1 1301.05  4516.0 1298.92  4528.7 1299.81
  4604.6 1295.14  4664.8 1297.47  4791.6 1292.21  4819.3 1293.68  4852.2 1291.84
  4857.8 1288.15  4874.3 1285.93  4896.3 1289.58  4902.0 1292.76  4977.1 1290.27
  5003.2 1285.37  5003.7 1284.87  5009.2 1285.37  5012.5 1287.29  5035.3 1292.04
  5105.9 1297.58  5191.1 1301.01  5304.0 1302.68  5412.2 1306.20  5426.8 1306.80
#Mann=6,-1,0
  4220.9    0.05       0  4528.7    0.12       0  5003.2    0.07       0
  5009.2    0.12       0  5304.0    0.05       0  5412.2    0.12       0
Bank Sta=5003.2,5009.2
Exp/Cntr=0.3,0.1

Type RM Length L Ch R = 1,31000,777,777,777
BEGIN DESCRIPTION:
BAILEY BRANCH 61.0
END DESCRIPTION:
XS GIS Cut Line= 3
      2818305.70     10206253.11      2818815.47     10206177.81
      2819755.70     10205753.10
#Sta/Elev= 30
  4484.7 1304.74  4616.1 1297.97  4626.2 1298.81  4653.6 1296.36  4658.7 1297.31
  4697.0 1295.49  4717.2 1296.11  4762.3 1293.66  4828.4 1292.14  4927.0 1286.09
  4980.0 1287.46  4990.1 1285.82  4996.0 1282.23  4996.5 1281.73  5002.0 1282.23
  5011.2 1282.67  5033.2 1287.08  5088.0 1286.46  5118.1 1294.40  5141.2 1287.74
  5175.8 1286.45  5329.4 1292.00  5463.7 1294.53  5494.0 1293.47  5592.8 1299.49
  5629.2 1299.92  5652.3 1300.52  5739.7 1303.66  5873.2 1309.29  6031.7 1313.86
#Mann=7,-1,0
  4484.7    0.05       0  4762.3    0.12       0  4996.0    0.07       0
  5002.0    0.12       0  5629.2    0.05       0  5652.3    0.12       0
  5739.7    0.05       0
Bank Sta=4996,5002
Exp/Cntr=0.3,0.1

Type RM Length L Ch R = 1,30223,223,223,223
BEGIN DESCRIPTION:
BAILEY BRANCH 60.0
END DESCRIPTION:
XS GIS Cut Line= 3
      2818155.68     10206553.11      2818672.89     10206905.98
      2820405.65     10207003.11
#Sta/Elev= 30
  4234.0 1301.02  4250.1 1300.29  4374.6 1294.88  4401.6 1293.27  4427.7 1297.31
  4507.7 1293.64  4513.8 1290.51  4543.6 1292.22  4558.2 1290.75  4621.5 1289.14
  4839.3 1291.52  4934.5 1285.79  4973.1 1284.16  4999.7 1276.98  5000.2 1276.48
  5006.6 1276.98  5023.2 1282.65  5077.6 1281.86  5093.3 1277.64  5099.9 1278.15
  5123.3 1281.52  5293.6 1281.47  5353.7 1284.54  5654.2 1288.23  5724.3 1291.16
  5975.0 1292.58  6084.8 1296.46  6094.8 1294.66  6420.8 1309.32  6595.6 1315.69
#Mann=10,-1,0
  4234.0    0.05       0  4250.1    0.12       0  4374.6    0.05       0
  4401.6    0.12       0  4558.2    0.05       0  4934.5    0.12       0
  4999.7    0.07       0  5006.6    0.12       0  5099.9    0.05       0
  6420.8    0.12       0
Bank Sta=4999.7,5006.6
Exp/Cntr=0.3,0.1

Type RM Length L Ch R = 1,30000,500,500,500
BEGIN DESCRIPTION:
BAILEY BRANCH 59.0
END DESCRIPTION:
XS GIS Cut Line= 3
      2818255.69     10206903.11      2818799.29     10207136.29
      2819942.59     10207528.79
#Sta/Elev= 30
  4408.5 1297.44  4441.1 1294.09  4452.0 1296.09  4484.7 1292.82  4576.6 1290.63
  4632.1 1287.06  4743.5 1286.22  4798.2 1288.87  4899.1 1284.85  4979.5 1281.62
  5003.5 1274.94  5008.8 1275.89  5017.3 1281.79  5047.8 1282.04  5159.8 1278.82
  5398.0 1277.68  5404.6 1274.65  5409.9 1276.04  5415.7 1273.06  5416.2 1272.56
  5422.6 1273.06  5435.9 1275.34  5441.2 1274.28  5467.1 1280.45  5535.4 1283.75
  5736.3 1287.83  5774.4 1286.96  5820.9 1290.27  5842.2 1289.00  6208.8 1309.15
#Mann=8,-1,0
  4408.5    0.12       0  4576.6    0.05       0  4632.1    0.12       0
  4743.5    0.05       0  4899.1    0.12       0  5047.8    0.05       0
  5415.7    0.07       0  5422.6    0.05       0
Bank Sta=5415.7,5422.6
Exp/Cntr=0.3,0.1

Type RM Length L Ch R = 1,29500,276,276,276
BEGIN DESCRIPTION:
BAILEY BRANCH 58.0
END DESCRIPTION:
XS GIS Cut Line= 3
      2818205.66     10207353.10      2818556.44     10207540.93
      2820005.71     10207653.11
#Sta/Elev= 30
  4602.1 1292.39  4640.9 1288.81  4906.0 1275.13  4955.6 1269.16  4971.8 1272.50
  4990.3 1267.85  4990.8 1267.35  4997.3 1267.85  5029.3 1273.67  5109.6 1274.49
  5149.7 1270.22  5169.7 1271.15  5199.8 1275.74  5216.9 1274.35  5250.0 1276.49
  5348.7 1272.20  5353.8 1275.28  5420.5 1277.49  5500.7 1276.54  5801.6 1284.26
  5851.8 1282.71  5901.9 1287.22  5932.0 1285.70  5962.1 1288.82  6032.3 1290.33
  6052.4 1294.16  6062.4 1291.30  6072.4 1291.76  6102.5 1295.31  6453.6 1315.29
#Mann=5,-1,0
  4602.1    0.05       0  4640.9    0.12       0  4990.3    0.07       0
  4997.3    0.12       0  5216.9    0.05       0
Bank Sta=4990.3,4997.3
Exp/Cntr=0.3,0.1

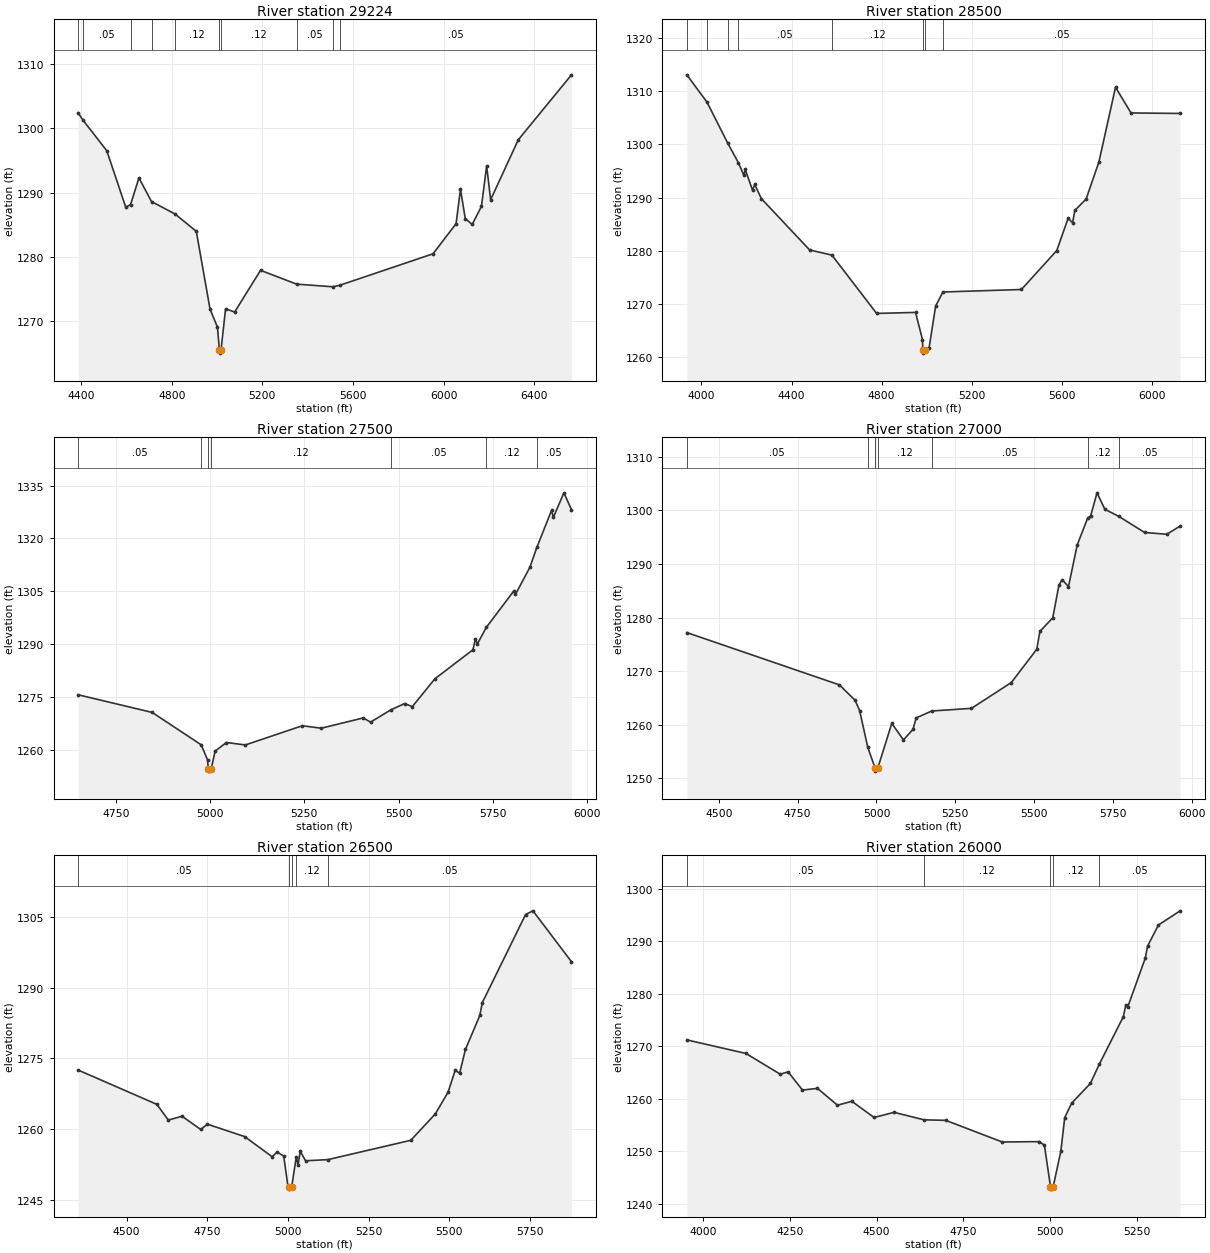
Type RM Length L Ch R = 1,29224,724,724,724
BEGIN DESCRIPTION:
Mapping XS 8b6faf9d
END DESCRIPTION:
XS GIS Cut Line= 4
      2817819.46     10207515.54      2818493.05     10207800.26
      2819097.22     10207904.43      2819916.62     10208057.20
#Sta/Elev= 30
  4387.1 1302.41  4407.6 1301.32  4513.3 1296.53  4596.9 1287.76  4618.2 1288.15
  4655.2 1292.31  4710.7 1288.63  4815.0 1286.69  4908.5 1284.00  4969.3 1271.87
  5001.8 1269.11  5010.5 1265.56  5011.0 1265.06  5017.7 1265.56  5037.8 1271.96
  5077.8 1271.45  5192.1 1277.94  5351.2 1275.79  5510.5 1275.38  5541.0 1275.60
  5953.7 1280.51  6055.4 1285.19  6074.8 1290.54  6096.1 1285.98  6126.6 1285.07
  6167.3 1287.87  6190.4 1294.18  6208.0 1288.91  6330.1 1298.24  6565.0 1308.34
#Mann=10,-1,0
  4387.1    0.12       0  4407.6    0.05       0  4618.2    0.12       0
  4710.7    0.05       0  4815.0    0.12       0  5010.5    0.07       0
  5017.7    0.12       0  5351.2    0.05       0  5510.5    0.12       0
  5541.0    0.05       0
Bank Sta=5010.5,5017.7
Exp/Cntr=0.3,0.1

Type RM Length L Ch R = 1,28500,1000,1000,1000
BEGIN DESCRIPTION:
BAILEY BRANCH 56.0
END DESCRIPTION:
XS GIS Cut Line= 4
      2817655.69     10207803.11      2818641.78     10208203.83
      2819125.89     10208411.58      2819721.45     10208452.98
#Sta/Elev= 30
  3935.6 1313.02  4024.9 1307.91  4116.5 1300.25  4164.4 1296.53  4188.6 1294.17
  4194.7 1295.28  4227.0 1291.38  4236.7 1292.46  4266.2 1289.79  4480.4 1280.16
  4579.2 1279.19  4777.6 1268.25  4950.2 1268.44  4981.0 1263.34  4982.8 1261.30
  4983.3 1260.80  4990.0 1261.30  5010.3 1261.77  5039.3 1269.62  5071.5 1272.27
  5419.9 1272.74  5576.7 1280.05  5626.8 1286.07  5646.9 1285.27  5656.9 1287.58
  5707.0 1289.72  5763.7 1296.68  5837.3 1310.69  5905.9 1305.87  6123.8 1305.77
#Mann=8,-1,0
  3935.6    0.12       0  4024.9    0.05       0  4116.5    0.12       0
  4164.4    0.05       0  4579.2    0.12       0  4982.8    0.07       0
  4990.0    0.12       0  5071.5    0.05       0
Bank Sta=4982.8,4990
Exp/Cntr=0.3,0.1

Type RM Length L Ch R = 1,27500,500,500,500
BEGIN DESCRIPTION:
BAILEY BRANCH 54.0
END DESCRIPTION:
XS GIS Cut Line= 3
      2818155.73     10208653.12      2818502.26     10208697.85
      2819455.66     10208603.11
#Sta/Elev= 30
  4650.6 1275.70  4846.5 1270.71  4976.5 1261.54  4993.4 1257.27  4995.6 1254.57
  4996.1 1254.07  5002.9 1254.57  5013.5 1259.75  5043.6 1262.18  5093.7 1261.49
  5244.6 1266.93  5294.9 1266.23  5406.2 1269.15  5425.5 1267.94  5478.8 1271.42
  5516.0 1273.22  5536.1 1272.34  5596.3 1280.26  5696.8 1288.45  5703.6 1291.57
  5708.6 1290.12  5732.3 1294.79  5804.4 1305.01  5809.4 1304.12  5847.6 1311.78
  5866.5 1317.54  5905.2 1327.93  5910.2 1326.02  5938.0 1332.93  5958.1 1328.13
#Mann=7,-1,0
  4650.6    0.05       0  4976.5    0.12       0  4995.6    0.07       0
  5002.9    0.12       0  5478.8    0.05       0  5732.3    0.12       0
  5866.5    0.05       0
Bank Sta=4995.6,5002.9
Exp/Cntr=0.3,0.1

Type RM Length L Ch R = 1,27000,500,500,500
BEGIN DESCRIPTION:
BAILEY BRANCH 53.0
END DESCRIPTION:
XS GIS Cut Line= 3
      2818005.67     10208803.10      2818480.69     10209172.57
      2819437.45     10209286.36
#Sta/Elev= 30
  4398.2 1277.19  4882.3 1267.43  4932.1 1264.56  4946.6 1262.62  4972.5 1255.75
  4996.1 1251.83  4996.6 1251.33  5003.8 1251.83  5048.6 1260.24  5085.6 1257.16
  5115.8 1259.12  5125.9 1261.26  5175.4 1262.55  5301.5 1263.05  5428.0 1267.87
  5508.6 1274.07  5518.6 1277.40  5559.4 1279.95  5579.0 1286.04  5589.1 1287.07
  5609.3 1285.77  5637.0 1293.54  5670.1 1298.54  5679.7 1298.97  5699.9 1303.27
  5724.7 1300.20  5769.0 1298.87  5850.9 1295.87  5921.4 1295.54  5963.5 1297.06
#Mann=7,-1,0
  4398.2    0.05       0  4972.5    0.12       0  4996.1    0.07       0
  5003.8    0.12       0  5175.4    0.05       0  5670.1    0.12       0
  5769.0    0.05       0
Bank Sta=4996.1,5003.8
Exp/Cntr=0.3,0.1

Type RM Length L Ch R = 1,26500,500,500,500
BEGIN DESCRIPTION:
BAILEY BRANCH 52.0
END DESCRIPTION:
XS GIS Cut Line= 3
      2817905.67     10209253.10      2818430.76     10209636.22
      2819236.08     10209987.75
#Sta/Elev= 30
  4350.0 1272.50  4593.7 1265.23  4629.3 1261.90  4671.9 1262.71  4729.7 1259.90
  4750.5 1261.02  4865.6 1258.40  4951.4 1254.10  4966.0 1255.15  4986.9 1254.27
  5000.0 1247.85  5003.9 1247.75  5004.4 1247.25  5011.6 1247.75  5025.8 1254.07
  5031.2 1252.38  5038.1 1255.27  5054.6 1253.26  5123.9 1253.51  5380.7 1257.61
  5456.4 1263.18  5496.4 1267.83  5518.2 1272.46  5532.1 1271.84  5550.1 1276.90
  5594.6 1284.09  5602.3 1286.81  5736.4 1305.49  5759.2 1306.28  5878.7 1295.48
#Mann=5,-1,0
  4350.0    0.05       0  5003.9    0.03       0  5011.6    0.05       0
  5025.8    0.12       0  5123.9    0.05       0
Bank Sta=5003.9,5011.6
Exp/Cntr=0.3,0.1

Type RM Length L Ch R = 1,26000,500,500,500
BEGIN DESCRIPTION:
BAILEY BRANCH 51.0
END DESCRIPTION:
XS GIS Cut Line= 3
      2817805.69     10209403.11      2818625.20     10210056.34
      2818980.72     10210178.12
#Sta/Elev= 30
  3952.0 1271.23  4122.5 1268.65  4221.8 1264.69  4244.3 1265.15  4285.9 1261.67
  4329.1 1262.00  4386.8 1258.79  4428.4 1259.53  4492.5 1256.45  4550.1 1257.43
  4636.9 1256.00  4699.1 1255.91  4862.4 1251.78  4969.7 1251.85  4984.1 1251.16
  5001.7 1243.30  5002.2 1242.80  5009.5 1243.30  5031.6 1250.03  5042.8 1256.43
  5062.9 1259.19  5116.8 1262.93  5142.2 1266.55  5211.9 1275.65  5219.3 1277.92
  5224.6 1277.49  5275.3 1286.81  5281.9 1289.11  5313.2 1293.11  5375.8 1295.82
#Mann=5,-1,0
  3952.0    0.05       0  4636.9    0.12       0  5001.7    0.07       0
  5009.5    0.12       0  5142.2    0.05       0
Bank Sta=5001.7,5009.5
Exp/Cntr=0.3,0.1

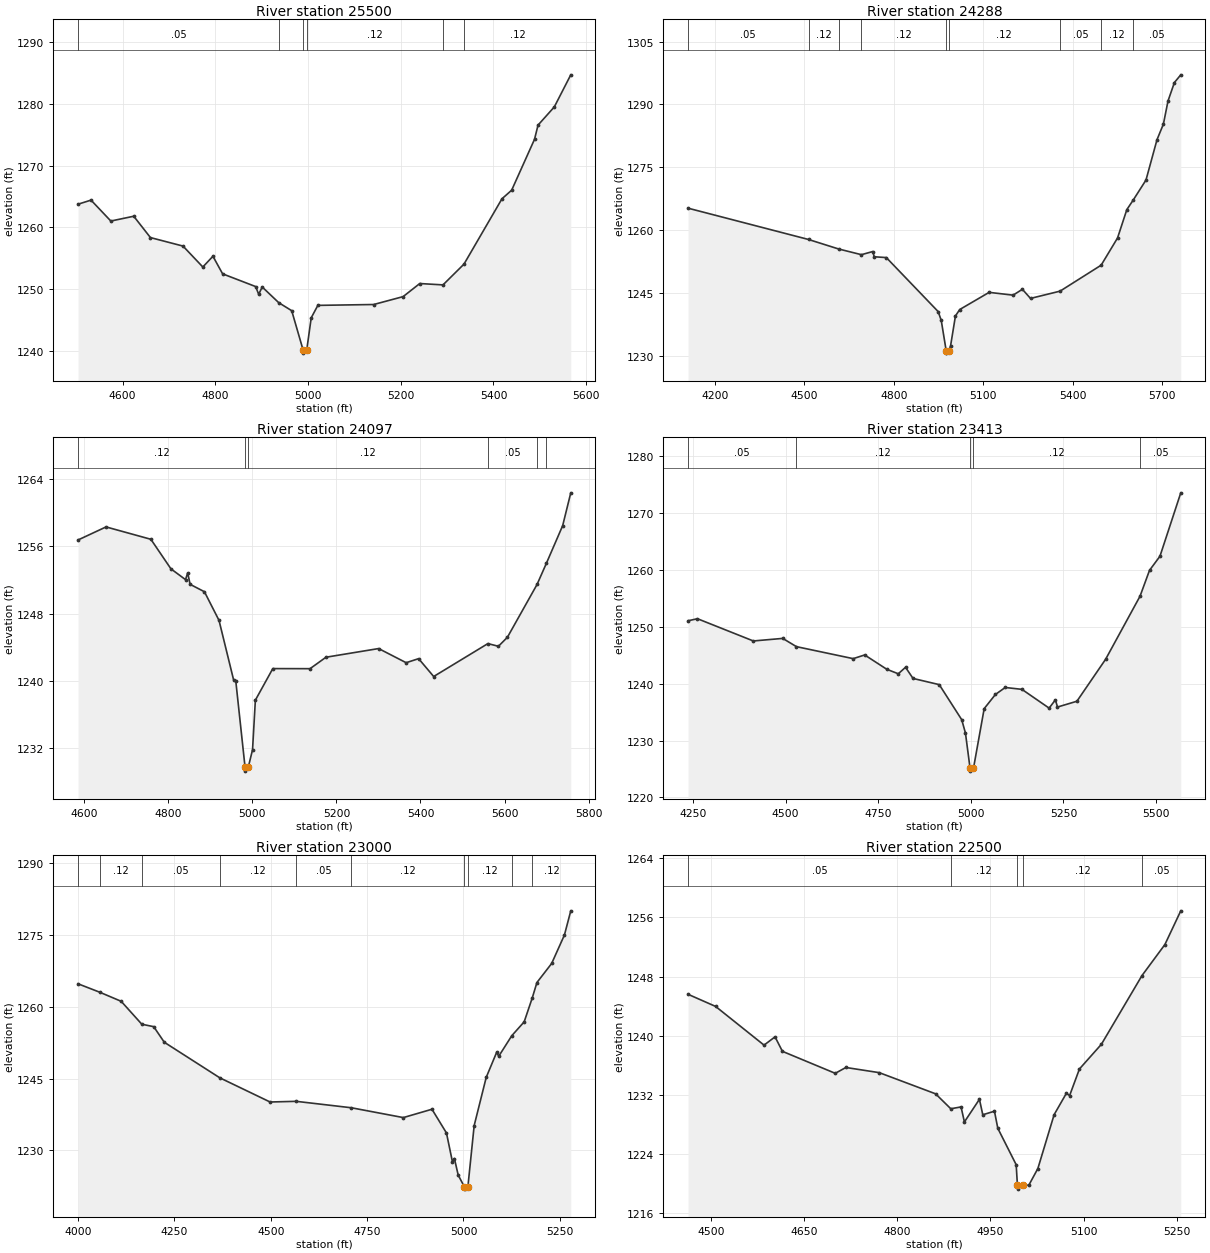
Type RM Length L Ch R = 1,25500,1212,1212,1212
BEGIN DESCRIPTION:
BAILEY BRANCH 50.0
END DESCRIPTION:
XS GIS Cut Line= 3
      2817905.66     10209903.08      2818232.50     10210276.03
      2818655.68     10210653.11
#Sta/Elev= 30
  4504.1 1263.74  4532.1 1264.40  4574.8 1261.01  4624.2 1261.79  4660.2 1258.33
  4730.5 1256.95  4773.2 1253.56  4795.0 1255.30  4815.9 1252.45  4887.1 1250.39
  4893.7 1249.14  4901.3 1250.32  4936.9 1247.78  4964.9 1246.48  4989.5 1240.10
  4990.0 1239.60  4997.3 1240.10  5007.0 1245.33  5021.3 1247.34  5141.7 1247.48
  5205.2 1248.76  5241.1 1250.88  5291.2 1250.66  5336.5 1254.03  5418.4 1264.62
  5439.3 1266.01  5488.6 1274.26  5496.2 1276.56  5531.3 1279.51  5566.8 1284.71
#Mann=6,-1,0
  4504.1    0.05       0  4936.9    0.12       0  4989.5    0.07       0
  4997.3    0.12       0  5291.2    0.05       0  5336.5    0.12       0
Bank Sta=4989.5,4997.3
Exp/Cntr=0.3,0.1

Type RM Length L Ch R = 1,24288,191,191,191
BEGIN DESCRIPTION:
BAILEY BRANCH 49.0
END DESCRIPTION:
XS GIS Cut Line= 4
      2817855.68     10209853.11      2817868.05     10210425.26
      2817979.16     10210848.87      2818530.65     10211178.09
#Sta/Elev= 30
  4110.1 1265.21  4514.2 1257.73  4615.2 1255.46  4691.5 1254.10  4729.4 1254.85
  4734.6 1253.60  4775.0 1253.41  4949.0 1240.50  4959.3 1238.38  4976.0 1231.08
  4976.5 1230.58  4983.9 1231.08  4990.3 1232.21  5006.9 1239.47  5021.3 1241.00
  5119.9 1245.10  5200.2 1244.43  5231.4 1245.83  5258.6 1243.65  5357.8 1245.39
  5495.5 1251.59  5550.5 1258.09  5581.7 1264.87  5602.9 1267.13  5645.9 1271.93
  5682.9 1281.58  5704.3 1285.29  5719.8 1290.82  5741.2 1295.23  5762.6 1297.07
#Mann=9,-1,0
  4110.1    0.05       0  4514.2    0.12       0  4615.2    0.05       0
  4691.5    0.12       0  4976.0    0.07       0  4983.9    0.12       0
  5357.8    0.05       0  5495.5    0.12       0  5602.9    0.05       0
Bank Sta=4976,4983.9
Exp/Cntr=0.3,0.1

Type RM Length L Ch R = 1,24097,684,684,684
BEGIN DESCRIPTION:
Mapping XS d9d0ce7d
END DESCRIPTION:
XS GIS Cut Line= 4
      2817652.76     10210355.78      2817791.66     10210869.70
      2818097.22     10211036.37      2818346.36     10211188.62
#Sta/Elev= 30
  4585.2 1256.74  4651.8 1258.29  4758.5 1256.82  4806.2 1253.31  4840.9 1252.03
  4846.1 1252.83  4851.8 1251.47  4885.9 1250.59  4920.6 1247.19  4955.3 1240.12
  4960.5 1239.99  4982.5 1229.78  4983.0 1229.28  4990.4 1229.78  5000.4 1231.83
  5007.1 1237.71  5048.6 1241.46  5137.2 1241.45  5175.1 1242.81  5300.4 1243.84
  5365.9 1242.16  5395.5 1242.64  5431.4 1240.52  5560.4 1244.43  5585.4 1244.11
  5606.8 1245.18  5677.3 1251.45  5699.4 1253.95  5738.3 1258.44  5757.6 1262.34
#Mann=6,-1,0
  4585.2    0.12       0  4982.5    0.07       0  4990.4    0.12       0
  5560.4    0.05       0  5677.3    0.12       0  5699.4    0.05       0
Bank Sta=4982.5,4990.4
Exp/Cntr=0.3,0.1

Type RM Length L Ch R = 1,23413,413,413,413
BEGIN DESCRIPTION:
Mapping XS d11b19e2
END DESCRIPTION:
XS GIS Cut Line= 4
      2817090.29     10211140.54      2817562.49     10211161.37
      2817937.49     10211105.81      2818368.08     10211314.16
#Sta/Elev= 30
  4236.6 1251.06  4262.0 1251.42  4412.8 1247.51  4492.2 1247.96  4529.2 1246.51
  4682.4 1244.40  4713.4 1245.05  4773.1 1242.53  4804.1 1241.74  4823.7 1242.88
  4843.9 1240.92  4914.7 1239.83  4975.3 1233.67  4985.4 1231.33  4997.9 1225.12
  4998.4 1224.62  5007.1 1225.12  5036.0 1235.61  5066.3 1238.10  5092.8 1239.33
  5137.9 1239.00  5211.3 1235.70  5228.3 1237.16  5233.9 1235.89  5286.3 1236.91
  5363.8 1244.29  5456.7 1255.38  5482.3 1259.93  5510.5 1262.41  5566.7 1273.56
#Mann=5,-1,0
  4236.6    0.05       0  4529.2    0.12       0  4997.9    0.07       0
  5007.1    0.12       0  5456.7    0.05       0
Bank Sta=4997.9,5007.1
Exp/Cntr=0.3,0.1

Type RM Length L Ch R = 1,23000,500,500,500
BEGIN DESCRIPTION:
BAILEY BRANCH 46.0
END DESCRIPTION:
XS GIS Cut Line= 3
      2817105.65     10211603.12      2818089.19     10211423.01
      2818355.72     10211503.12
#Sta/Elev= 30
  4000.1 1264.75  4056.2 1263.00  4112.0 1261.10  4165.5 1256.32  4196.4 1255.81
  4223.8 1252.56  4367.9 1245.14  4498.3 1240.10  4566.0 1240.24  4709.0 1238.90
  4843.9 1236.85  4918.2 1238.59  4955.8 1233.64  4971.4 1227.59  4976.4 1228.31
  4986.3 1224.84  5002.2 1222.43  5002.7 1221.93  5011.4 1222.43  5027.7 1235.19
  5059.0 1245.25  5086.1 1250.48  5091.4 1249.64  5125.3 1253.93  5157.4 1256.82
  5178.4 1261.81  5190.5 1265.02  5228.7 1268.99  5261.8 1274.92  5278.3 1279.97
#Mann=10,-1,0
  4000.1    0.05       0  4056.2    0.12       0  4165.5    0.05       0
  4367.9    0.12       0  4566.0    0.05       0  4709.0    0.12       0
  5002.2    0.07       0  5011.4    0.12       0  5125.3    0.05       0
  5178.4    0.12       0
Bank Sta=5002.2,5011.4
Exp/Cntr=0.3,0.1

Type RM Length L Ch R = 1,22500,500,500,500
BEGIN DESCRIPTION:
BAILEY BRANCH 45.0
END DESCRIPTION:
XS GIS Cut Line= 3
      2817455.68     10211703.11      2817954.05     10211903.09
      2818205.73     10211853.10
#Sta/Elev= 30
  4463.0 1245.62  4507.4 1243.98  4585.4 1238.75  4603.1 1239.87  4615.0 1237.91
  4700.1 1234.94  4717.2 1235.73  4771.0 1235.03  4861.7 1232.17  4886.2 1230.15
  4902.7 1230.40  4908.1 1228.37  4932.3 1231.43  4937.7 1229.34  4956.5 1229.82
  4961.9 1227.51  4991.5 1222.59  4993.5 1219.79  4994.0 1219.29  5002.9 1219.79
  5011.9 1219.83  5026.4 1222.07  5052.6 1229.35  5072.4 1232.25  5077.5 1231.92
  5093.4 1235.53  5128.7 1238.86  5194.1 1248.15  5231.0 1252.34  5256.6 1256.90
#Mann=5,-1,0
  4463.0    0.05       0  4886.2    0.12       0  4993.5    0.07       0
  5002.9    0.12       0  5194.1    0.05       0
Bank Sta=4993.5,5002.9
Exp/Cntr=0.3,0.1

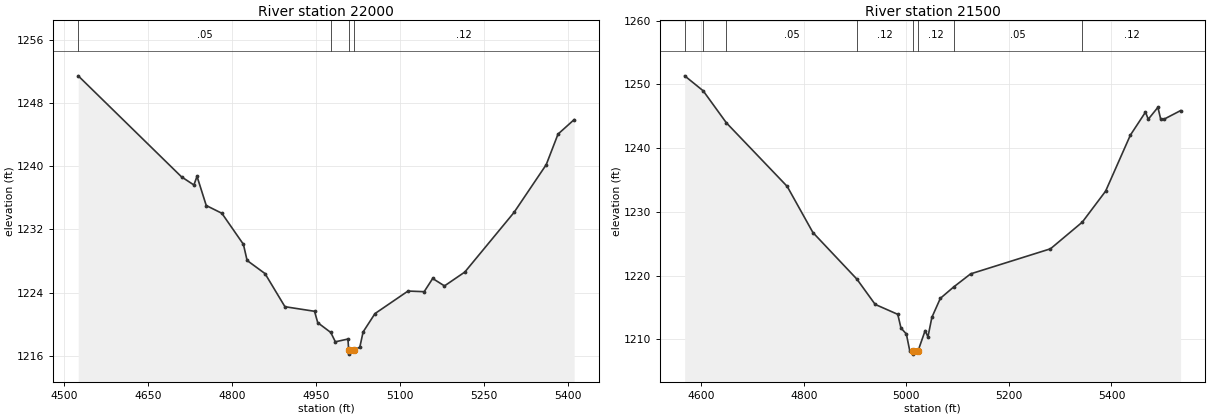
Type RM Length L Ch R = 1,22000,500,500,500
BEGIN DESCRIPTION:
BAILEY BRANCH 44.0
END DESCRIPTION:
XS GIS Cut Line= 3
      2817715.29     10212821.06      2817933.83     10212399.43
      2818155.69     10212053.10
#Sta/Elev= 30
  4525.1 1251.42  4709.7 1238.64  4731.8 1237.61  4737.4 1238.70  4753.9 1235.01
  4781.8 1234.03  4820.3 1230.10  4826.9 1228.06  4858.9 1226.40  4894.5 1222.21
  4947.4 1221.63  4953.1 1220.19  4976.4 1218.95  4984.6 1217.77  5007.1 1218.12
  5008.4 1216.71  5008.9 1216.21  5017.8 1216.71  5028.3 1217.09  5034.2 1219.02
  5055.4 1221.34  5114.4 1224.19  5143.3 1224.11  5158.5 1225.78  5179.6 1224.84
  5216.0 1226.60  5303.9 1234.14  5361.4 1240.18  5382.5 1244.05  5411.3 1245.88
#Mann=4,-1,0
  4525.1    0.05       0  4976.4    0.12       0  5008.4    0.07       0
  5017.8    0.12       0
Bank Sta=5008.4,5017.8
Exp/Cntr=0.3,0.1

Type RM Length L Ch R = 1,21500,500,500,500
BEGIN DESCRIPTION:
BAILEY BRANCH 43.0
END DESCRIPTION:
XS GIS Cut Line= 3
      2818005.65     10212803.14      2818355.57     10212549.29
      2818155.70     10212053.14
#Sta/Elev= 30
  4567.7 1251.33  4603.8 1248.98  4649.1 1243.95  4767.6 1233.99  4817.8 1226.75
  4903.6 1219.44  4939.2 1215.48  4983.3 1213.92  4989.5 1211.78  5000.0 1210.84
  5006.7 1208.19  5013.2 1208.18  5013.7 1207.68  5022.8 1208.18  5036.7 1211.38
  5042.1 1210.38  5049.8 1213.45  5066.3 1216.43  5092.4 1218.22  5125.4 1220.27
  5281.1 1224.20  5343.1 1228.38  5388.6 1233.24  5436.9 1242.03  5466.4 1245.64
  5471.8 1244.52  5490.6 1246.39  5496.0 1244.55  5502.6 1244.53  5534.9 1245.88
#Mann=8,-1,0
  4567.7    0.05       0  4603.8    0.12       0  4649.1    0.05       0
  4903.6    0.12       0  5013.2    0.07       0  5022.8    0.12       0
  5092.4    0.05       0  5343.1    0.12       0
Bank Sta=5013.2,5022.8
Exp/Cntr=0.3,0.1