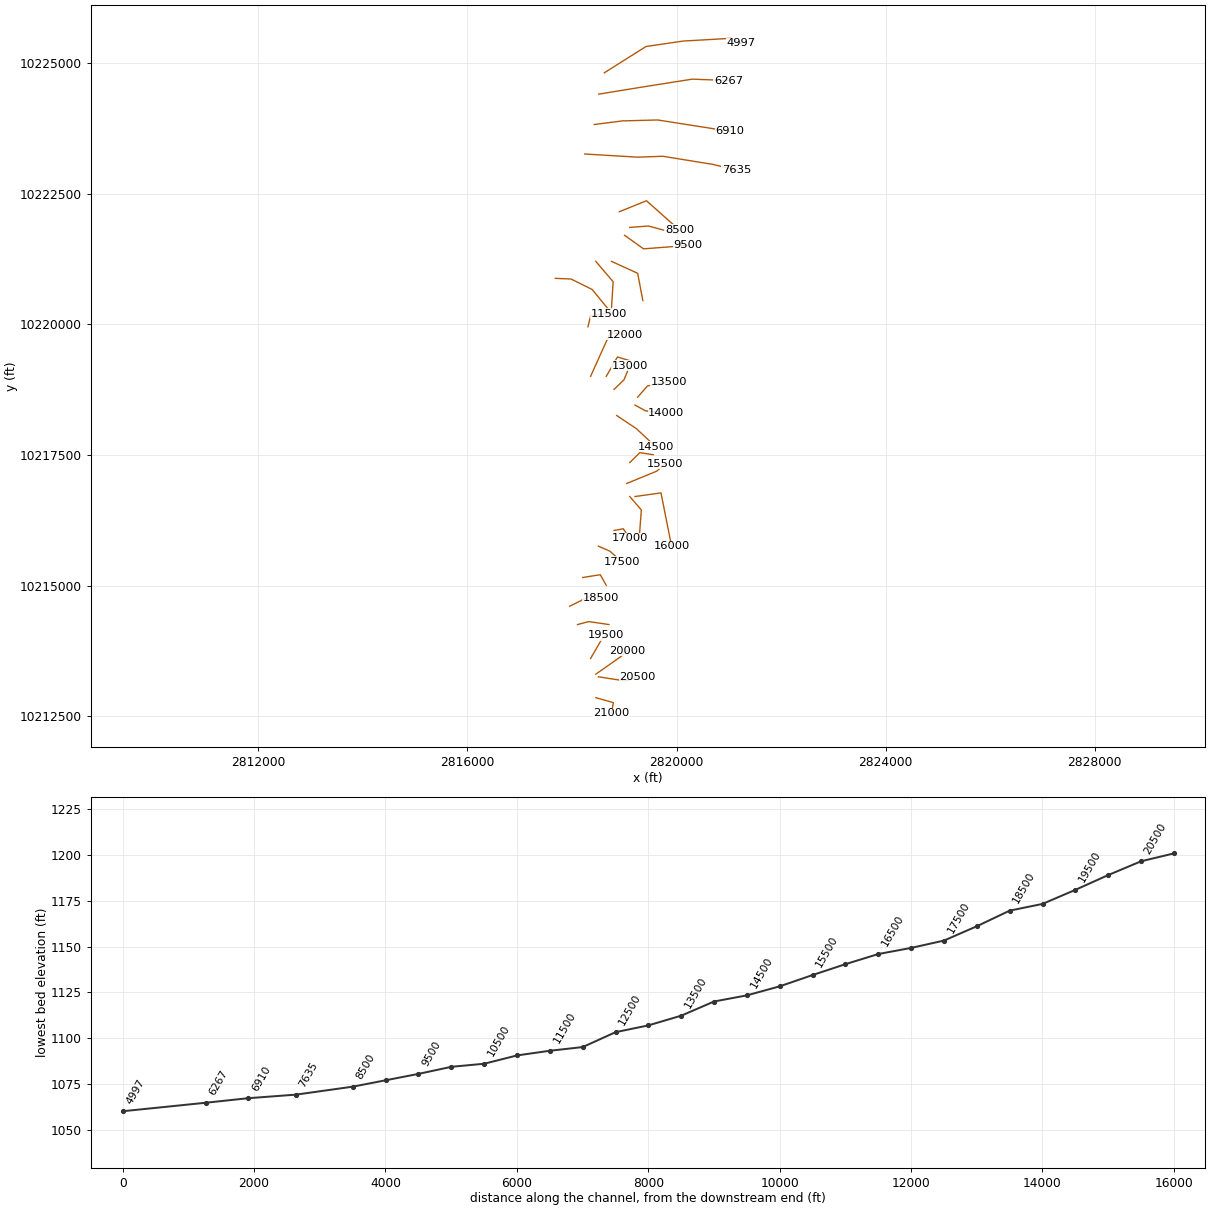
HEC-RAS study BAILEY BRANCH.prj: BAILEY BRANCH Base Level Engineering

--- BAILEY BRANCH.g01 (geometry) --- (continued)

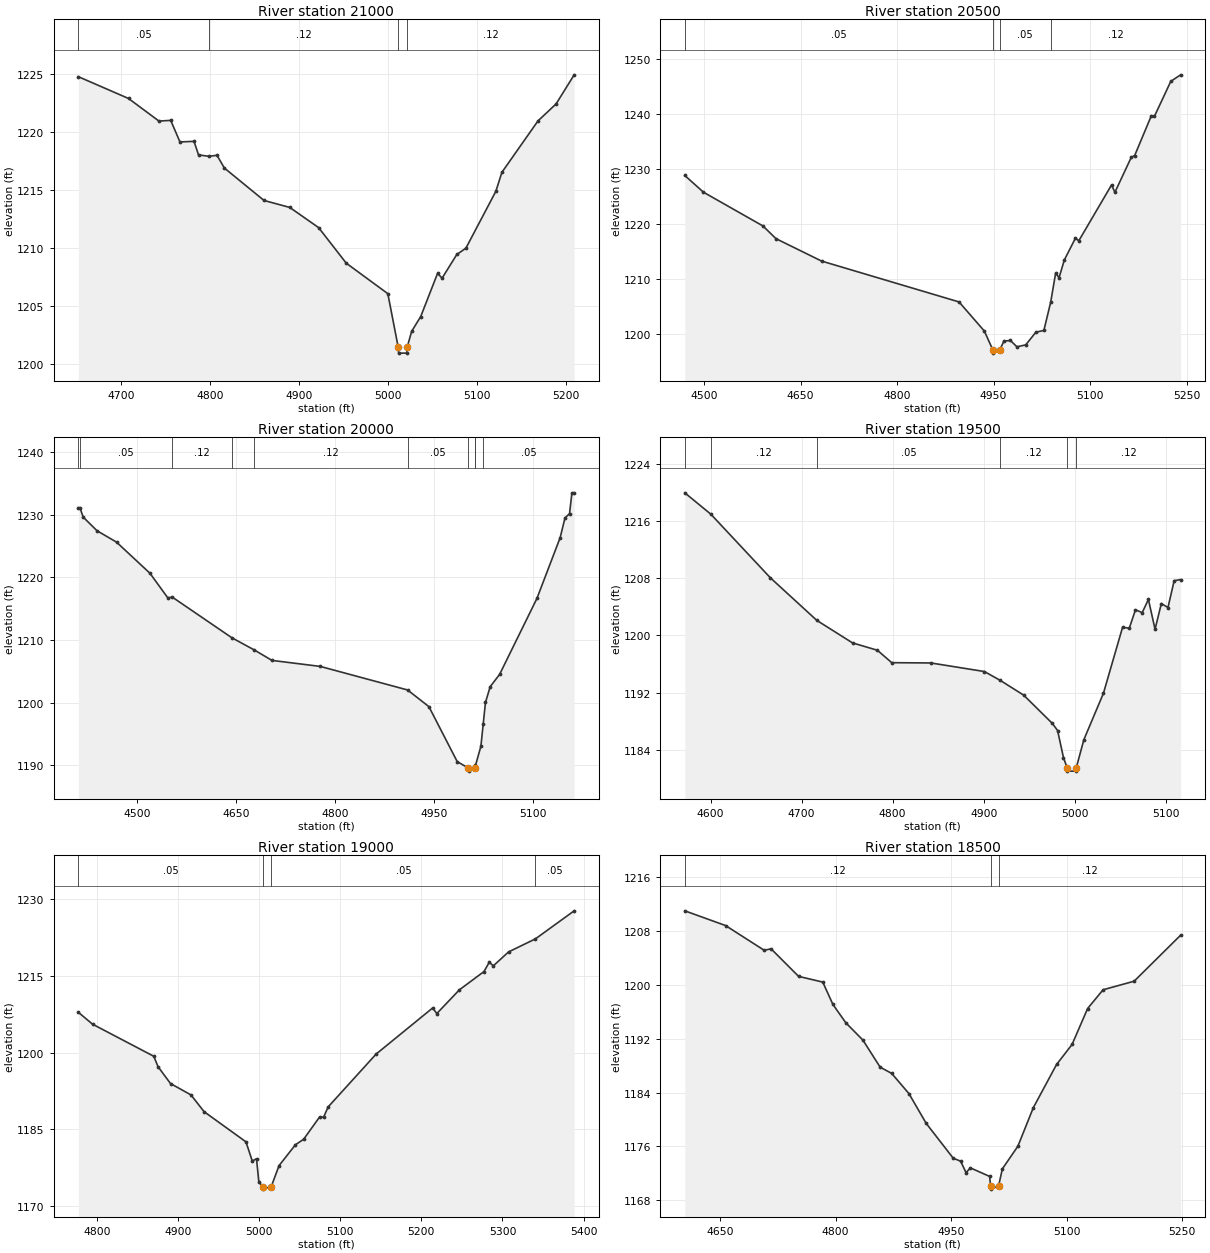
Type RM Length L Ch R = 1,21000,500,500,500
BEGIN DESCRIPTION:
BAILEY BRANCH 42.0
END DESCRIPTION:
XS GIS Cut Line= 3
      2818455.67     10212853.12      2818790.65     10212759.55
      2818755.68     10212553.09
#Sta/Elev= 30
  4652.2 1224.76  4708.6 1222.88  4742.8 1220.93  4756.0 1220.99  4766.4 1219.13
  4782.2 1219.18  4787.3 1218.01  4799.1 1217.89  4808.0 1217.98  4816.3 1216.88
  4860.9 1214.08  4889.8 1213.48  4922.2 1211.74  4953.3 1208.67  5000.0 1206.04
  5011.7 1201.41  5012.2 1200.91  5021.2 1200.91  5021.7 1201.41  5026.8 1202.79
  5037.0 1204.07  5055.9 1207.79  5061.0 1207.38  5077.5 1209.42  5087.7 1209.96
  5121.4 1214.87  5128.2 1216.51  5168.8 1220.95  5189.1 1222.41  5209.4 1224.92
#Mann=4,-1,0
  4652.2    0.05       0  4799.1    0.12       0  5011.7    0.07       0
  5021.7    0.12       0
Bank Sta=5011.7,5021.7
Exp/Cntr=0.3,0.1

Type RM Length L Ch R = 1,20500,500,500,500
BEGIN DESCRIPTION:
BAILEY BRANCH 41.0
END DESCRIPTION:
XS GIS Cut Line= 3
      2818505.70     10213253.11      2819029.19     10213171.58
      2819255.66     10213253.10
#Sta/Elev= 30
  4470.2 1228.88  4499.1 1225.85  4591.6 1219.71  4611.9 1217.40  4682.7 1213.33
  4896.4 1205.90  4935.7 1200.61  4949.2 1197.10  4949.7 1196.60  4959.3 1197.10
  4966.1 1198.79  4976.2 1198.90  4986.3 1197.75  5000.0 1198.10  5015.8 1200.41
  5028.2 1200.72  5038.8 1205.87  5046.5 1211.15  5051.8 1210.31  5060.0 1213.53
  5077.2 1217.48  5082.5 1217.02  5133.3 1227.15  5138.6 1225.83  5164.0 1232.18
  5169.3 1232.50  5194.7 1239.60  5200.0 1239.63  5225.4 1245.98  5240.7 1247.17
#Mann=4,-1,0
  4470.2    0.05       0  4949.2    0.03       0  4959.3    0.05       0
  5038.8    0.12       0
Bank Sta=4949.2,4959.3
Exp/Cntr=0.3,0.1

Type RM Length L Ch R = 1,20000,500,500,500
BEGIN DESCRIPTION:
BAILEY BRANCH 40.0
END DESCRIPTION:
XS GIS Cut Line= 3
      2818455.70     10213303.13      2818938.25     10213641.73
      2819055.65     10213753.08
#Sta/Elev= 30
  4410.5 1231.10  4412.9 1231.10  4417.9 1229.60  4438.8 1227.43  4468.4 1225.61
  4519.0 1220.65  4546.0 1216.73  4553.0 1216.83  4643.3 1210.34  4677.4 1208.39
  4703.8 1206.74  4777.0 1205.78  4909.4 1202.02  4941.7 1199.36  4984.6 1190.59
  5001.3 1189.57  5001.8 1189.07  5011.4 1189.57  5012.3 1189.97  5020.5 1193.05
  5024.0 1196.59  5027.4 1200.03  5034.6 1202.55  5048.8 1204.50  5105.4 1216.63
  5140.6 1226.33  5147.9 1229.47  5154.8 1230.16  5158.4 1233.48  5161.8 1233.48
#Mann=10,-1,0
  4410.5    0.12       0  4412.9    0.05       0  4553.0    0.12       0
  4643.3    0.05       0  4677.4    0.12       0  4909.4    0.05       0
  5001.3    0.05       0  5011.4    0.05       0  5012.3    0.12       0
  5024.0    0.05       0
Bank Sta=5001.3,5011.4
Exp/Cntr=0.3,0.1

Type RM Length L Ch R = 1,19500,500,500,500
BEGIN DESCRIPTION:
BAILEY BRANCH 39.0
END DESCRIPTION:
XS GIS Cut Line= 3
      2818355.69     10213603.13      2818570.48     10213973.79
      2818655.68     10214053.11
#Sta/Elev= 30
  4571.6 1219.97  4600.2 1216.98  4665.6 1208.07  4716.7 1202.10  4755.9 1198.95
  4783.2 1197.92  4799.0 1196.18  4842.0 1196.14  4900.8 1194.94  4918.2 1193.70
  4943.9 1191.64  4975.4 1187.68  4981.2 1186.68  4987.7 1182.88  4991.6 1181.49
  4992.1 1180.99  5001.3 1180.99  5001.8 1181.49  5010.1 1185.40  5031.6 1191.90
  5052.6 1201.13  5060.0 1201.01  5066.8 1203.59  5074.2 1203.19  5081.0 1205.04
  5088.3 1200.86  5095.2 1204.46  5102.5 1203.90  5109.3 1207.66  5116.4 1207.82
#Mann=6,-1,0
  4571.6    0.05       0  4600.2    0.12       0  4716.7    0.05       0
  4918.2    0.12       0  4991.6    0.07       0  5001.8    0.12       0
Bank Sta=4991.6,5001.8
Exp/Cntr=0.3,0.1

Type RM Length L Ch R = 1,19000,500,500,500
BEGIN DESCRIPTION:
BAILEY BRANCH 38.0
END DESCRIPTION:
XS GIS Cut Line= 3
      2818105.72     10214253.12      2818321.45     10214309.58
      2818705.72     10214253.11
#Sta/Elev= 30
  4777.0 1207.90  4794.6 1205.57  4870.0 1199.30  4875.4 1197.23  4890.7 1193.96
  4915.9 1191.74  4932.0 1188.47  4983.7 1182.56  4991.5 1178.80  4996.7 1179.26
  4999.6 1174.69  5004.6 1173.81  5005.1 1173.31  5014.9 1173.81  5024.5 1177.91
  5044.7 1181.99  5054.8 1183.06  5074.4 1187.40  5079.5 1187.41  5085.1 1189.40
  5144.2 1199.73  5214.0 1208.76  5219.0 1207.65  5246.9 1212.30  5277.2 1215.87
  5283.7 1217.69  5288.8 1217.00  5307.5 1219.71  5340.7 1222.27  5388.4 1227.75
#Mann=4,-1,0
  4777.0    0.05       0  5004.6    0.05       0  5014.9    0.05       0
  5340.7    0.05       0
Bank Sta=5004.6,5014.9
Exp/Cntr=0.3,0.1

Type RM Length L Ch R = 1,18500,500,500,500
BEGIN DESCRIPTION:
BAILEY BRANCH 37.0
END DESCRIPTION:
XS GIS Cut Line= 3
      2817955.69     10214603.12      2818309.24     10214781.28
      2818555.73     10214753.11
#Sta/Elev= 30
  4604.1 1211.00  4657.1 1208.81  4707.3 1205.13  4716.1 1205.36  4751.9 1201.26
  4783.3 1200.41  4796.5 1197.08  4813.2 1194.37  4835.5 1191.78  4857.8 1187.77
  4872.8 1186.84  4895.2 1183.84  4917.6 1179.42  4952.7 1174.24  4962.4 1173.79
  4969.4 1172.09  4975.0 1172.80  5000.0 1171.53  5001.3 1170.14  5001.8 1169.64
  5011.7 1170.14  5016.6 1172.66  5036.7 1176.01  5056.8 1181.75  5087.0 1188.17
  5107.1 1191.14  5127.3 1196.48  5147.4 1199.27  5187.7 1200.54  5248.1 1207.38
#Mann=3,-1,0
  4604.1    0.12       0  5001.3    0.07       0  5011.7    0.12       0
Bank Sta=5001.3,5011.7
Exp/Cntr=0.3,0.1

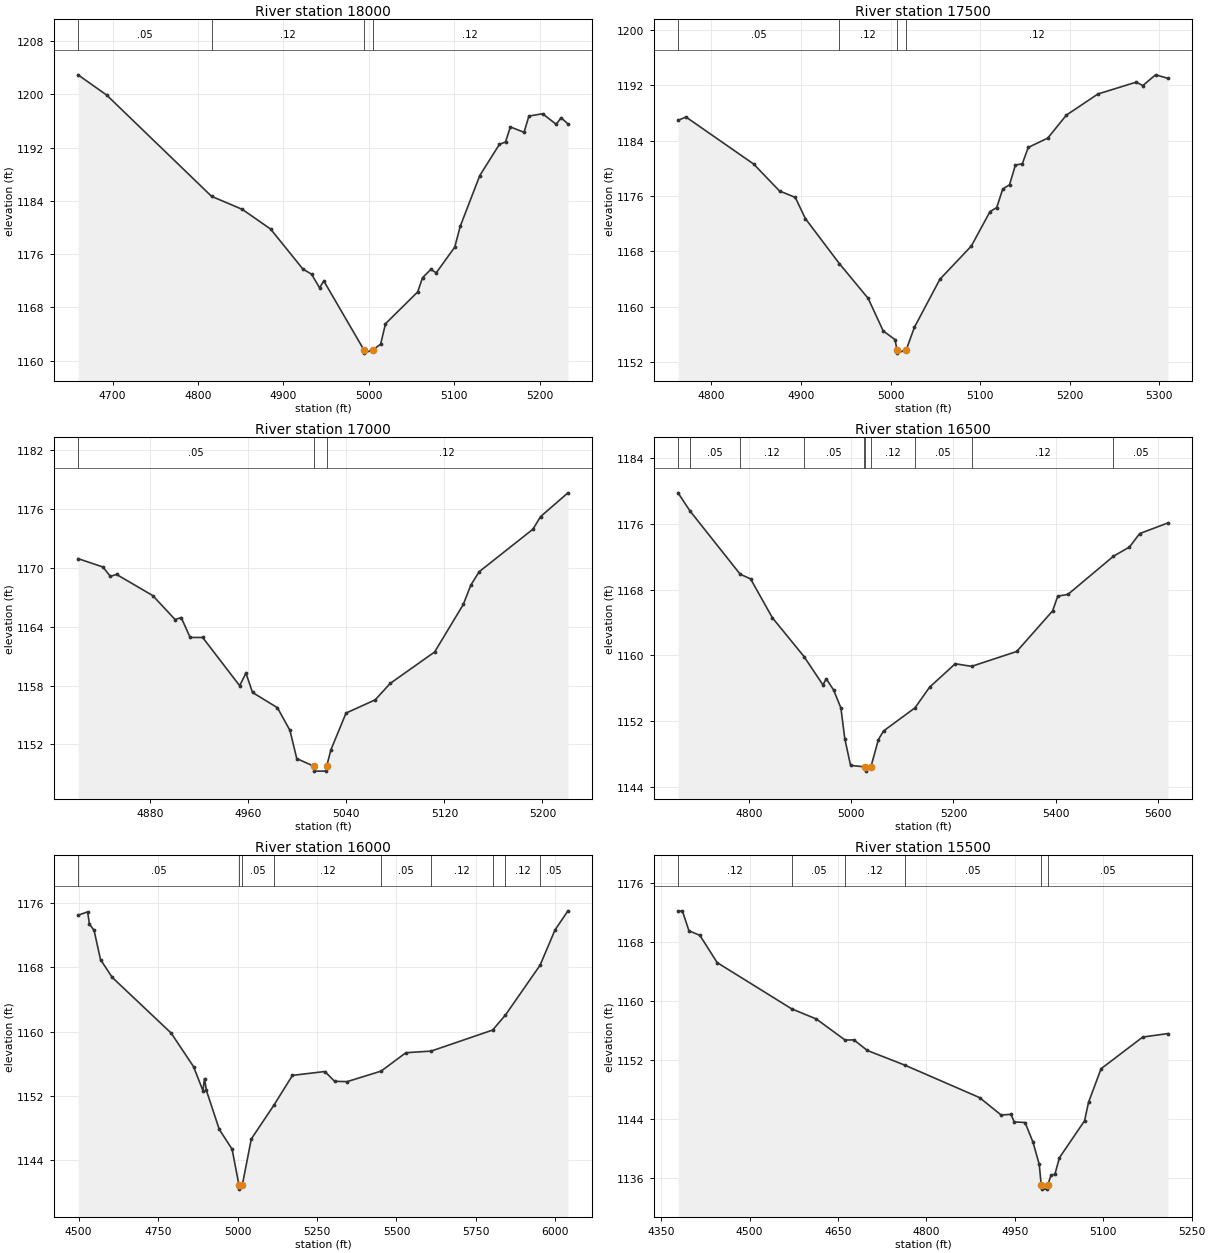
Type RM Length L Ch R = 1,18000,500,500,500
BEGIN DESCRIPTION:
BAILEY BRANCH 36.0
END DESCRIPTION:
XS GIS Cut Line= 3
      2818205.71     10215153.12      2818541.90     10215206.50
      2818655.71     10215003.07
#Sta/Elev= 30
  4659.6 1202.94  4693.2 1199.89  4815.9 1184.68  4852.0 1182.71  4885.1 1179.75
  4922.8 1173.75  4933.0 1172.97  4942.3 1170.93  4947.3 1171.96  4994.2 1161.61
  4994.7 1161.11  5004.6 1161.61  5013.8 1162.44  5019.5 1165.53  5057.2 1170.31
  5062.9 1172.45  5072.6 1173.70  5078.9 1173.18  5100.6 1177.05  5107.0 1180.17
  5129.9 1187.80  5152.8 1192.48  5160.0 1192.85  5165.7 1195.11  5181.7 1194.30
  5187.4 1196.74  5203.4 1197.09  5219.3 1195.51  5225.1 1196.49  5233.1 1195.56
#Mann=4,-1,0
  4659.6    0.05       0  4815.9    0.12       0  4994.2    0.07       0
  5004.6    0.12       0
Bank Sta=4994.2,5004.6
Exp/Cntr=0.3,0.1

Type RM Length L Ch R = 1,17500,500,500,500
BEGIN DESCRIPTION:
BAILEY BRANCH 35.0
END DESCRIPTION:
XS GIS Cut Line= 3
      2818505.71     10215753.10      2818723.18     10215657.88
      2818955.67     10215453.12
#Sta/Elev= 30
  4762.6 1186.91  4771.5 1187.40  4847.1 1180.60  4876.0 1176.71  4893.6 1175.78
  4904.8 1172.73  4942.8 1166.22  4975.0 1161.19  4991.8 1156.49  5005.0 1155.23
  5007.2 1153.78  5007.7 1153.28  5017.6 1153.78  5026.6 1157.00  5055.1 1163.95
  5090.2 1168.75  5111.1 1173.73  5118.6 1174.31  5125.3 1176.99  5132.9 1177.61
  5139.5 1180.47  5147.1 1180.62  5153.8 1183.00  5175.6 1184.35  5196.4 1187.67
  5231.6 1190.72  5274.3 1192.43  5281.8 1191.94  5296.0 1193.49  5309.8 1192.99
#Mann=4,-1,0
  4762.6    0.05       0  4942.8    0.12       0  5007.2    0.07       0
  5017.6    0.12       0
Bank Sta=5007.2,5017.6
Exp/Cntr=0.3,0.1

Type RM Length L Ch R = 1,17000,500,500,500
BEGIN DESCRIPTION:
BAILEY BRANCH 34.0
END DESCRIPTION:
XS GIS Cut Line= 3
      2818805.72     10216053.12      2818981.71     10216085.82
      2819105.68     10215903.11
#Sta/Elev= 30
  4821.0 1170.94  4841.3 1170.09  4847.4 1169.13  4852.4 1169.33  4882.0 1167.17
  4900.2 1164.73  4905.2 1164.93  4912.5 1162.90  4922.7 1162.90  4952.9 1157.98
  4958.0 1159.27  4963.4 1157.29  4983.7 1155.74  4993.9 1153.43  4999.5 1150.55
  5013.4 1149.77  5013.9 1149.27  5023.4 1149.27  5023.9 1149.77  5027.4 1151.46
  5039.7 1155.19  5063.5 1156.54  5075.8 1158.22  5112.0 1161.42  5135.4 1166.27
  5141.5 1168.23  5148.3 1169.60  5192.3 1173.95  5198.4 1175.22  5220.8 1177.65
#Mann=3,-1,0
  4821.0    0.05       0  5013.4    0.05       0  5023.9    0.12       0
Bank Sta=5013.4,5023.9
Exp/Cntr=0.3,0.1

Type RM Length L Ch R = 1,16500,500,500,500
BEGIN DESCRIPTION:
BAILEY BRANCH 33.0
END DESCRIPTION:
XS GIS Cut Line= 3
      2819105.68     10216703.11      2819326.83     10216446.05
      2819280.68     10215828.07
#Sta/Elev= 30
  4660.9 1179.75  4684.5 1177.54  4782.6 1169.86  4803.0 1169.29  4845.6 1164.57
  4907.6 1159.85  4944.5 1156.41  4951.1 1157.15  4965.4 1155.79  4979.7 1153.61
  4987.3 1149.88  4998.6 1146.63  5025.8 1146.45  5027.8 1146.43  5028.3 1145.93
  5038.3 1146.43  5053.1 1149.76  5063.1 1150.81  5124.7 1153.62  5153.4 1156.14
  5203.5 1158.98  5235.4 1158.66  5323.8 1160.47  5394.0 1165.40  5404.1 1167.19
  5424.1 1167.41  5513.2 1172.05  5544.4 1173.16  5564.5 1174.80  5619.7 1176.09
#Mann=10,-1,0
  4660.9    0.12       0  4684.5    0.05       0  4782.6    0.12       0
  4907.6    0.05       0  5025.8    0.12       0  5027.8    0.05       0
  5038.3    0.12       0  5124.7    0.05       0  5235.4    0.12       0
  5513.2    0.05       0
Bank Sta=5027.8,5038.3
Exp/Cntr=0.3,0.1

Type RM Length L Ch R = 1,16000,500,500,500
BEGIN DESCRIPTION:
BAILEY BRANCH 32.0
END DESCRIPTION:
XS GIS Cut Line= 3
      2819205.66     10216703.11      2819702.62     10216772.63
      2819905.68     10215753.15
#Sta/Elev= 30
  4498.2 1174.49  4528.5 1174.90  4533.9 1173.39  4548.7 1172.59  4568.9 1168.97
  4605.4 1166.76  4791.0 1159.82  4861.7 1155.63  4891.1 1152.65  4896.1 1154.15
  4902.1 1152.67  4942.5 1147.83  4982.9 1145.36  5004.5 1140.89  5005.0 1140.39
  5015.0 1140.89  5043.3 1146.64  5114.1 1150.82  5172.8 1154.55  5274.8 1155.03
  5305.4 1153.81  5344.8 1153.77  5451.7 1155.08  5529.7 1157.37  5609.0 1157.57
  5802.6 1160.19  5843.0 1162.07  5951.8 1168.26  5998.8 1172.65  6039.5 1175.03
#Mann=9,-1,0
  4498.2    0.05       0  5004.5    0.05       0  5015.0    0.05       0
  5114.1    0.12       0  5451.7    0.05       0  5609.0    0.12       0
  5802.6    0.05       0  5843.0    0.12       0  5951.8    0.05       0
Bank Sta=5004.5,5015
Exp/Cntr=0.3,0.1

Type RM Length L Ch R = 1,15500,500,500,500
BEGIN DESCRIPTION:
BAILEY BRANCH 31.0
END DESCRIPTION:
XS GIS Cut Line= 3
      2819048.64     10216953.05      2819623.54     10217189.44
      2819780.69     10217328.12
#Sta/Elev= 30
  4378.4 1172.22  4386.0 1172.17  4397.0 1169.51  4415.5 1168.89  4444.9 1165.19
  4571.2 1158.92  4613.1 1157.54  4661.9 1154.68  4676.8 1154.71  4699.6 1153.27
  4764.1 1151.25  4890.1 1146.87  4926.6 1144.51  4943.4 1144.60  4948.8 1143.58
  4967.3 1143.49  4980.7 1140.82  4991.3 1137.81  4994.7 1134.95  4995.2 1134.45
  5004.8 1134.45  5005.3 1134.95  5011.3 1136.32  5018.0 1136.50  5025.5 1138.71
  5068.2 1143.73  5074.9 1146.23  5096.2 1150.79  5166.9 1155.09  5209.6 1155.56
#Mann=6,-1,0
  4378.4    0.12       0  4571.2    0.05       0  4661.9    0.12       0
  4764.1    0.05       0  4994.7    0.05       0  5005.3    0.05       0
Bank Sta=4994.7,5005.3
Exp/Cntr=0.3,0.1

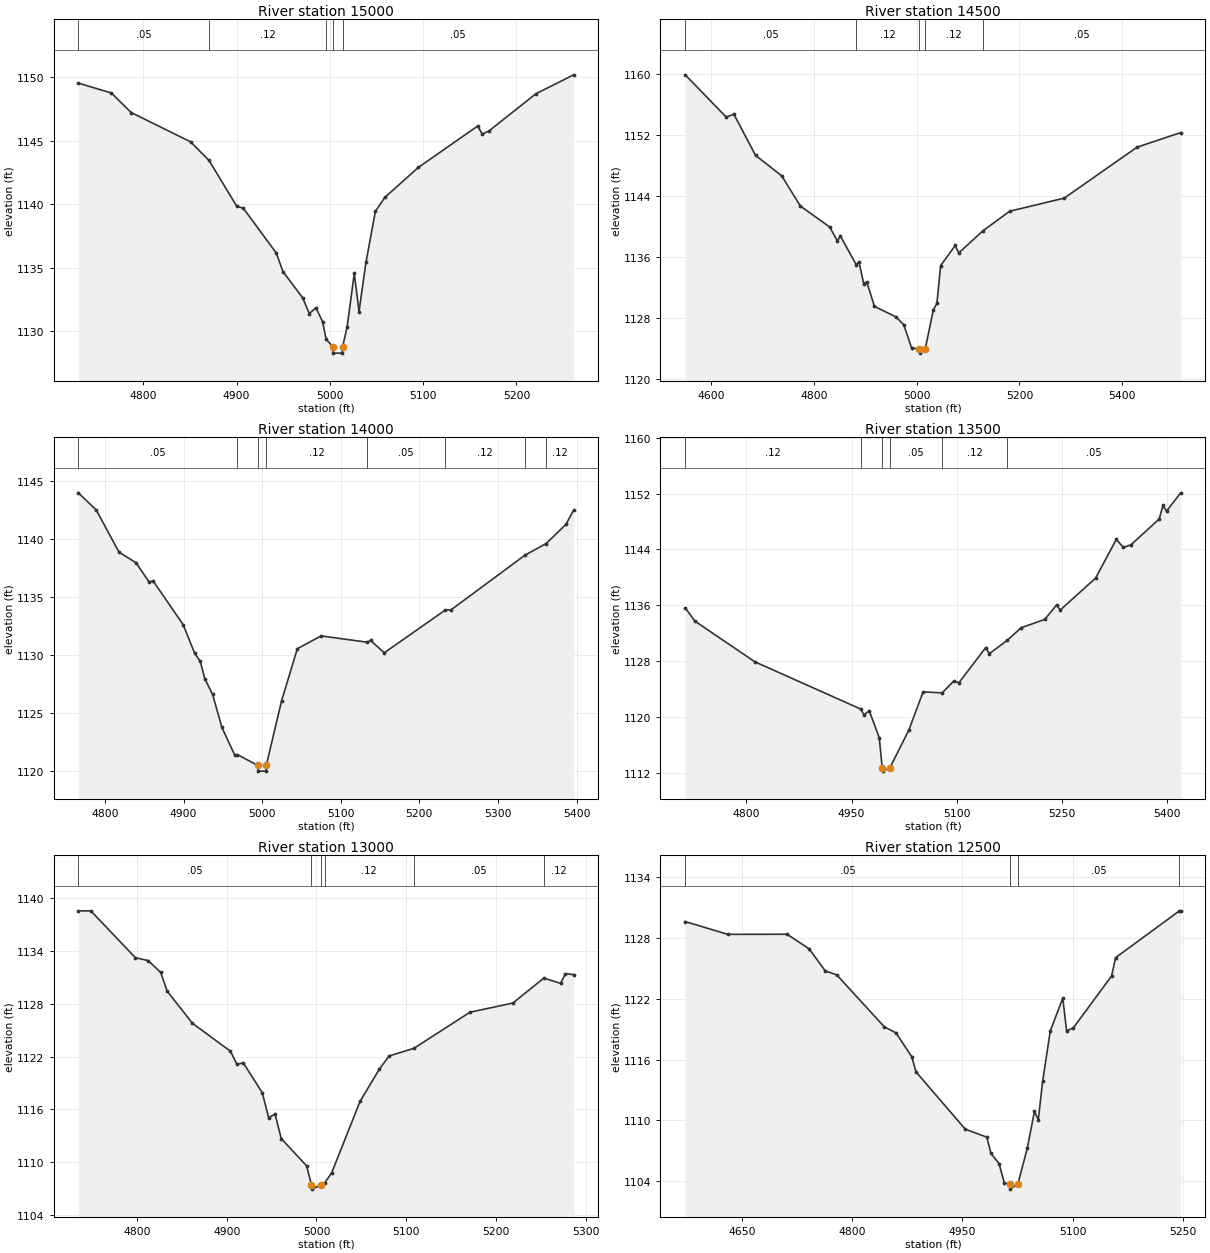
Type RM Length L Ch R = 1,15000,500,500,500
BEGIN DESCRIPTION:
BAILEY BRANCH 30.0
END DESCRIPTION:
XS GIS Cut Line= 3
      2819105.66     10217353.09      2819297.41     10217542.46
      2819555.73     10217503.10
#Sta/Elev= 30
  4730.5 1149.56  4765.9 1148.78  4787.1 1147.24  4850.8 1144.93  4870.6 1143.46
  4900.2 1139.86  4907.3 1139.70  4942.6 1136.17  4949.8 1134.70  4970.9 1132.64
  4978.0 1131.40  4985.1 1131.85  4992.2 1130.77  4996.0 1129.39  5003.1 1128.78
  5003.6 1128.28  5013.2 1128.28  5013.7 1128.78  5018.5 1130.33  5026.2 1134.56
  5031.3 1131.56  5038.7 1135.43  5048.8 1139.45  5058.9 1140.55  5094.8 1142.91
  5158.3 1146.17  5163.4 1145.54  5170.2 1145.77  5220.8 1148.72  5261.3 1150.21
#Mann=5,-1,0
  4730.5    0.05       0  4870.6    0.12       0  4996.0    0.05       0
  5003.1    0.05       0  5013.7    0.05       0
Bank Sta=5003.1,5013.7
Exp/Cntr=0.3,0.1

Type RM Length L Ch R = 1,14500,500,500,500
BEGIN DESCRIPTION:
BAILEY BRANCH 29.0
END DESCRIPTION:
XS GIS Cut Line= 3
      2818855.70     10218253.10      2819230.12     10218003.31
      2819605.68     10217653.11
#Sta/Elev= 30
  4549.9 1159.85  4629.5 1154.31  4644.5 1154.68  4686.6 1149.29  4737.6 1146.60
  4773.7 1142.65  4830.8 1139.89  4845.8 1138.07  4851.8 1138.69  4882.4 1134.96
  4887.9 1135.31  4896.9 1132.46  4902.9 1132.70  4917.9 1129.48  4960.0 1128.09
  4975.0 1127.06  4990.0 1124.06  5005.5 1123.85  5006.0 1123.35  5016.5 1123.85
  5032.5 1129.02  5039.4 1129.87  5046.7 1134.83  5075.0 1137.47  5081.9 1136.49
  5129.4 1139.42  5181.0 1141.96  5287.1 1143.68  5428.7 1150.36  5513.5 1152.27
#Mann=5,-1,0
  4549.9    0.05       0  4882.4    0.12       0  5005.5    0.07       0
  5016.5    0.12       0  5129.4    0.05       0
Bank Sta=5005.5,5016.5
Exp/Cntr=0.3,0.1

Type RM Length L Ch R = 1,14000,500,500,500
BEGIN DESCRIPTION:
BAILEY BRANCH 28.0
END DESCRIPTION:
XS GIS Cut Line= 3
      2819205.70     10218453.10      2819411.07     10218341.15
      2819805.64     10218303.12
#Sta/Elev= 30
  4766.1 1143.99  4788.9 1142.51  4817.8 1138.88  4839.7 1137.95  4855.8 1136.33
  4861.5 1136.37  4899.5 1132.62  4914.1 1130.16  4921.3 1129.45  4927.0 1127.97
  4936.9 1126.61  4948.8 1123.76  4965.0 1121.38  4968.6 1121.41  4994.3 1120.49
  4994.8 1119.99  5004.8 1119.99  5005.3 1120.49  5024.7 1126.05  5044.8 1130.55
  5075.0 1131.65  5133.4 1131.11  5138.1 1131.26  5155.3 1130.19  5233.0 1133.88
  5240.4 1133.90  5334.5 1138.62  5361.2 1139.61  5386.4 1141.26  5396.4 1142.50
#Mann=8,-1,0
  4766.1    0.05       0  4968.6    0.12       0  4994.3    0.07       0
  5005.3    0.12       0  5133.4    0.05       0  5233.0    0.12       0
  5334.5    0.05       0  5361.2    0.12       0
Bank Sta=4994.3,5005.3
Exp/Cntr=0.3,0.1

Type RM Length L Ch R = 1,13500,500,500,500
BEGIN DESCRIPTION:
BAILEY BRANCH 27.0
END DESCRIPTION:
XS GIS Cut Line= 3
      2819255.68     10218603.11      2819444.77     10218819.41
      2819855.64     10218903.10
#Sta/Elev= 30
  4712.7 1135.62  4726.5 1133.73  4811.9 1127.91  4962.7 1121.15  4967.6 1120.34
  4975.2 1120.87  4989.4 1117.05  4993.6 1112.75  4994.1 1112.25  5004.7 1112.75
  5031.5 1118.10  5052.0 1123.60  5079.1 1123.46  5095.8 1125.16  5103.0 1124.90
  5141.3 1129.94  5146.4 1129.06  5172.0 1130.98  5191.8 1132.78  5225.4 1133.97
  5242.4 1136.05  5247.5 1135.31  5298.0 1139.89  5327.5 1145.43  5337.7 1144.28
  5348.6 1144.67  5388.7 1148.35  5394.1 1150.29  5399.2 1149.48  5419.3 1152.10
#Mann=6,-1,0
  4712.7    0.12       0  4962.7    0.05       0  4993.6    0.05       0
  5004.7    0.05       0  5079.1    0.12       0  5172.0    0.05       0
Bank Sta=4993.6,5004.7
Exp/Cntr=0.3,0.1

Type RM Length L Ch R = 1,13000,500,500,500
BEGIN DESCRIPTION:
BAILEY BRANCH 26.0
END DESCRIPTION:
XS GIS Cut Line= 3
      2818805.70     10218753.13      2818995.88     10218938.25
      2819105.67     10219203.09
#Sta/Elev= 30
  4734.6 1138.59  4748.6 1138.58  4798.2 1133.26  4812.4 1132.93  4826.5 1131.58
  4833.5 1129.47  4861.8 1125.80  4904.2 1122.62  4911.4 1121.13  4918.4 1121.31
  4939.7 1117.89  4946.7 1115.06  4953.8 1115.48  4960.8 1112.68  4989.1 1109.58
  4994.4 1107.44  4994.9 1106.94  5005.5 1107.44  5009.2 1107.64  5017.0 1108.80
  5048.6 1116.92  5070.2 1120.60  5081.0 1122.09  5108.6 1122.95  5171.1 1127.06
  5218.9 1128.10  5253.4 1130.94  5272.1 1130.34  5277.5 1131.45  5286.7 1131.33
#Mann=6,-1,0
  4734.6    0.05       0  4994.4    0.05       0  5005.5    0.05       0
  5009.2    0.12       0  5108.6    0.05       0  5253.4    0.12       0
Bank Sta=4994.4,5005.5
Exp/Cntr=0.3,0.1

Type RM Length L Ch R = 1,12500,500,500,500
BEGIN DESCRIPTION:
BAILEY BRANCH 25.0
END DESCRIPTION:
XS GIS Cut Line= 3
      2818655.71     10219003.15      2818868.92     10219373.00
      2819105.72     10219303.10
#Sta/Elev= 30
  4573.1 1129.62  4630.8 1128.36  4711.6 1128.37  4741.8 1126.92  4763.4 1124.76
  4779.2 1124.36  4843.8 1119.24  4859.6 1118.65  4881.2 1116.29  4886.9 1114.80
  4954.0 1109.14  4983.2 1108.36  4988.9 1106.75  5000.0 1105.74  5007.1 1103.82
  5014.4 1103.73  5014.9 1103.23  5025.5 1103.73  5038.3 1107.26  5048.1 1110.91
  5053.3 1110.07  5059.2 1113.87  5069.6 1118.84  5086.6 1122.06  5091.8 1118.84
  5100.9 1119.13  5153.0 1124.26  5158.4 1126.06  5245.3 1130.68  5246.9 1130.68
#Mann=4,-1,0
  4573.1    0.05       0  5014.4    0.05       0  5025.5    0.05       0
  5245.3    0.12       0
Bank Sta=5014.4,5025.5
Exp/Cntr=0.3,0.1

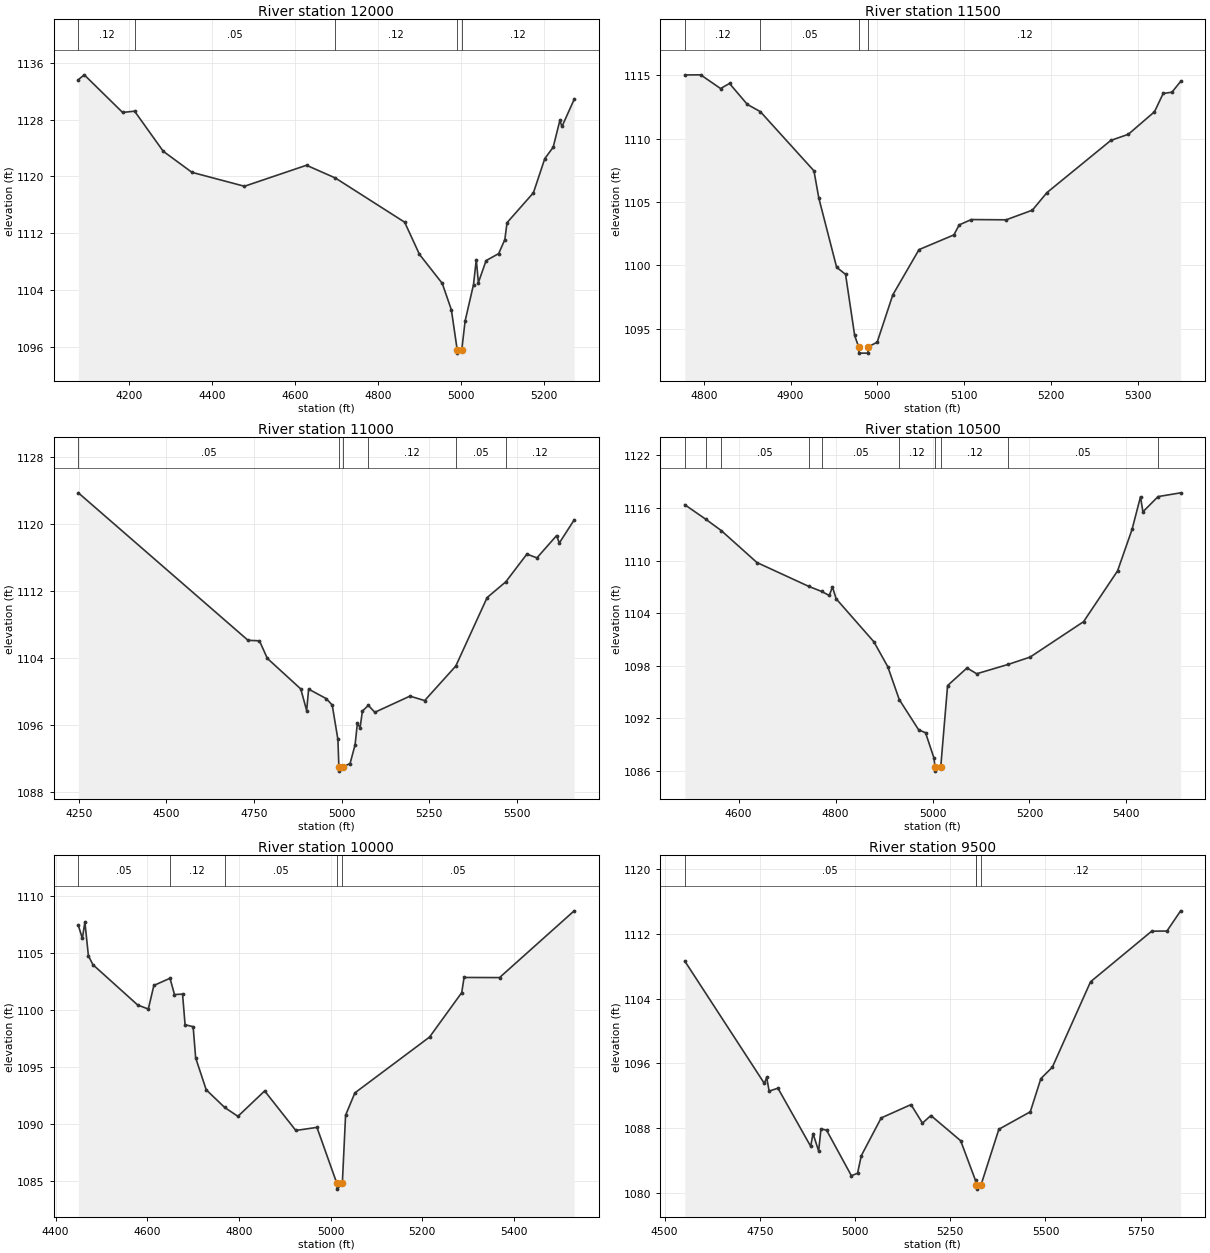
Type RM Length L Ch R = 1,12000,500,500,500
BEGIN DESCRIPTION:
BAILEY BRANCH 24.0
END DESCRIPTION:
XS GIS Cut Line= 3
      2818355.68     10219003.10      2818735.40     10219843.93
      2819005.73     10219803.10
#Sta/Elev= 30
  4077.4 1133.62  4091.7 1134.30  4184.2 1129.00  4213.1 1129.18  4282.2 1123.53
  4351.5 1120.56  4478.1 1118.60  4627.8 1121.56  4697.5 1119.76  4864.5 1113.54
  4900.3 1109.00  4955.2 1104.92  4977.2 1101.20  4991.2 1095.59  4991.7 1095.09
  5002.4 1095.59  5010.4 1099.63  5030.6 1104.74  5037.3 1108.27  5042.4 1105.03
  5061.0 1108.13  5091.3 1109.11  5106.2 1111.09  5111.5 1113.47  5175.1 1117.68
  5202.6 1122.50  5222.8 1124.10  5238.9 1127.87  5244.0 1127.02  5273.4 1130.84
#Mann=5,-1,0
  4077.4    0.12       0  4213.1    0.05       0  4697.5    0.12       0
  4991.2    0.07       0  5002.4    0.12       0
Bank Sta=4991.2,5002.4
Exp/Cntr=0.3,0.1

Type RM Length L Ch R = 1,11500,500,500,500
BEGIN DESCRIPTION:
BAILEY BRANCH 23.0
END DESCRIPTION:
XS GIS Cut Line= 3
      2818305.68     10219953.11      2818358.06     10220168.74
      2818705.66     10220203.11
#Sta/Elev= 30
  4778.1 1115.01  4796.4 1115.02  4819.3 1113.94  4829.6 1114.34  4850.1 1112.69
  4865.1 1112.12  4926.9 1107.45  4932.5 1105.30  4953.0 1099.85  4963.3 1099.29
  4973.8 1094.47  4978.3 1093.58  4978.8 1093.08  4989.0 1093.08  4989.5 1093.58
  4999.7 1093.94  5017.7 1097.67  5047.9 1101.24  5088.1 1102.40  5094.2 1103.19
  5108.2 1103.61  5148.3 1103.59  5178.5 1104.35  5195.2 1105.73  5268.9 1109.85
  5289.0 1110.33  5319.2 1112.11  5329.2 1113.55  5339.3 1113.65  5349.3 1114.50
#Mann=4,-1,0
  4778.1    0.12       0  4865.1    0.05       0  4978.3    0.07       0
  4989.5    0.12       0
Bank Sta=4978.3,4989.5
Exp/Cntr=0.3,0.1

Type RM Length L Ch R = 1,11000,500,500,500
BEGIN DESCRIPTION:
BAILEY BRANCH 22.0
END DESCRIPTION:
XS GIS Cut Line= 4
      2817680.72     10220878.11      2817980.86     10220866.01
      2818384.95     10220666.59      2818805.66     10220153.14
#Sta/Elev= 30
  4249.0 1123.77  4733.2 1106.15  4765.8 1106.09  4788.3 1103.99  4883.7 1100.34
  4900.5 1097.76  4906.1 1100.32  4956.6 1099.18  4973.5 1098.41  4989.7 1094.30
  4992.4 1091.02  4992.9 1090.52  5004.2 1091.02  5024.4 1091.43  5038.7 1093.67
  5045.2 1096.22  5053.1 1095.72  5059.5 1097.69  5076.5 1098.38  5095.0 1097.55
  5195.2 1099.48  5237.2 1098.95  5326.1 1103.08  5415.5 1111.26  5468.8 1113.14
  5528.9 1116.45  5557.6 1116.00  5613.6 1118.66  5621.5 1117.78  5663.8 1120.53
#Mann=6,-1,0
  4249.0    0.05       0  4992.4    0.03       0  5004.2    0.05       0
  5076.5    0.12       0  5326.1    0.05       0  5468.8    0.12       0
Bank Sta=4992.4,5004.2
Exp/Cntr=0.3,0.1

Type RM Length L Ch R = 1,10500,500,500,500
BEGIN DESCRIPTION:
BAILEY BRANCH 21.0
END DESCRIPTION:
XS GIS Cut Line= 3
      2818455.69     10221203.10      2818787.44     10220814.17
      2818755.69     10220303.15
#Sta/Elev= 30
  4488.8 1116.37  4532.0 1114.72  4563.9 1113.43  4637.6 1109.78  4744.5 1107.06
  4771.1 1106.48  4786.9 1106.02  4793.5 1106.99  4801.2 1105.64  4879.1 1100.73
  4907.7 1097.89  4931.4 1094.14  4971.4 1090.69  4985.6 1090.36  5003.0 1087.47
  5005.1 1086.48  5005.6 1085.98  5017.0 1086.48  5031.1 1095.74  5071.2 1097.75
  5091.2 1097.09  5155.9 1098.15  5201.4 1098.99  5311.7 1103.03  5381.8 1108.82
  5411.8 1113.56  5429.2 1117.28  5434.2 1115.56  5465.4 1117.30  5512.0 1117.73
#Mann=10,-1,0
  4488.8    0.05       0  4532.0    0.12       0  4563.9    0.05       0
  4744.5    0.12       0  4771.1    0.05       0  4931.4    0.12       0
  5005.1    0.07       0  5017.0    0.12       0  5155.9    0.05       0
  5465.4    0.12       0
Bank Sta=5005.1,5017
Exp/Cntr=0.3,0.1

Type RM Length L Ch R = 1,10000,500,500,500
BEGIN DESCRIPTION:
BAILEY BRANCH 20.0
END DESCRIPTION:
XS GIS Cut Line= 3
      2818755.64     10221203.13      2819256.57     10220975.33
      2819355.68     10220453.15
#Sta/Elev= 30
  4449.7 1107.45  4458.5 1106.31  4464.0 1107.74  4471.7 1104.78  4481.6 1104.00
  4579.3 1100.46  4602.4 1100.11  4614.5 1102.18  4649.7 1102.81  4659.5 1101.38
  4677.1 1101.42  4682.6 1098.73  4700.2 1098.56  4705.7 1095.82  4728.7 1093.02
  4769.0 1091.47  4797.9 1090.69  4856.2 1092.92  4924.2 1089.45  4970.3 1089.72
  5013.8 1084.80  5014.3 1084.30  5025.7 1084.80  5032.8 1090.79  5053.1 1092.75
  5216.0 1097.65  5286.2 1101.55  5291.3 1102.88  5368.7 1102.87  5531.5 1108.73
#Mann=5,-1,0
  4449.7    0.05       0  4649.7    0.12       0  4769.0    0.05       0
  5013.8    0.05       0  5025.7    0.05       0
Bank Sta=5013.8,5025.7
Exp/Cntr=0.3,0.1

Type RM Length L Ch R = 1,9500,500,500,500
BEGIN DESCRIPTION:
BAILEY BRANCH 19.0
END DESCRIPTION:
XS GIS Cut Line= 3
      2819005.64     10221703.14      2819369.09     10221443.09
      2820221.48     10221508.54
#Sta/Elev= 30
  4553.1 1108.66  4762.0 1093.52  4768.1 1094.26  4774.5 1092.57  4797.6 1092.93
  4883.6 1085.74  4889.8 1087.31  4904.5 1085.16  4910.7 1087.91  4925.4 1087.73
  4990.5 1082.10  5006.6 1082.40  5016.6 1084.59  5068.7 1089.25  5147.0 1090.90
  5177.1 1088.61  5199.2 1089.55  5277.4 1086.43  5316.4 1081.51  5318.7 1080.94
  5319.2 1080.44  5330.7 1080.94  5377.7 1087.85  5460.2 1090.01  5488.0 1094.12
  5518.1 1095.53  5618.4 1106.10  5778.9 1112.36  5819.0 1112.38  5854.9 1114.88
#Mann=4,-1,0
  4553.1    0.05       0  5316.4    0.12       0  5318.7    0.05       0
  5330.7    0.12       0
Bank Sta=5318.7,5330.7
Exp/Cntr=0.3,0.1

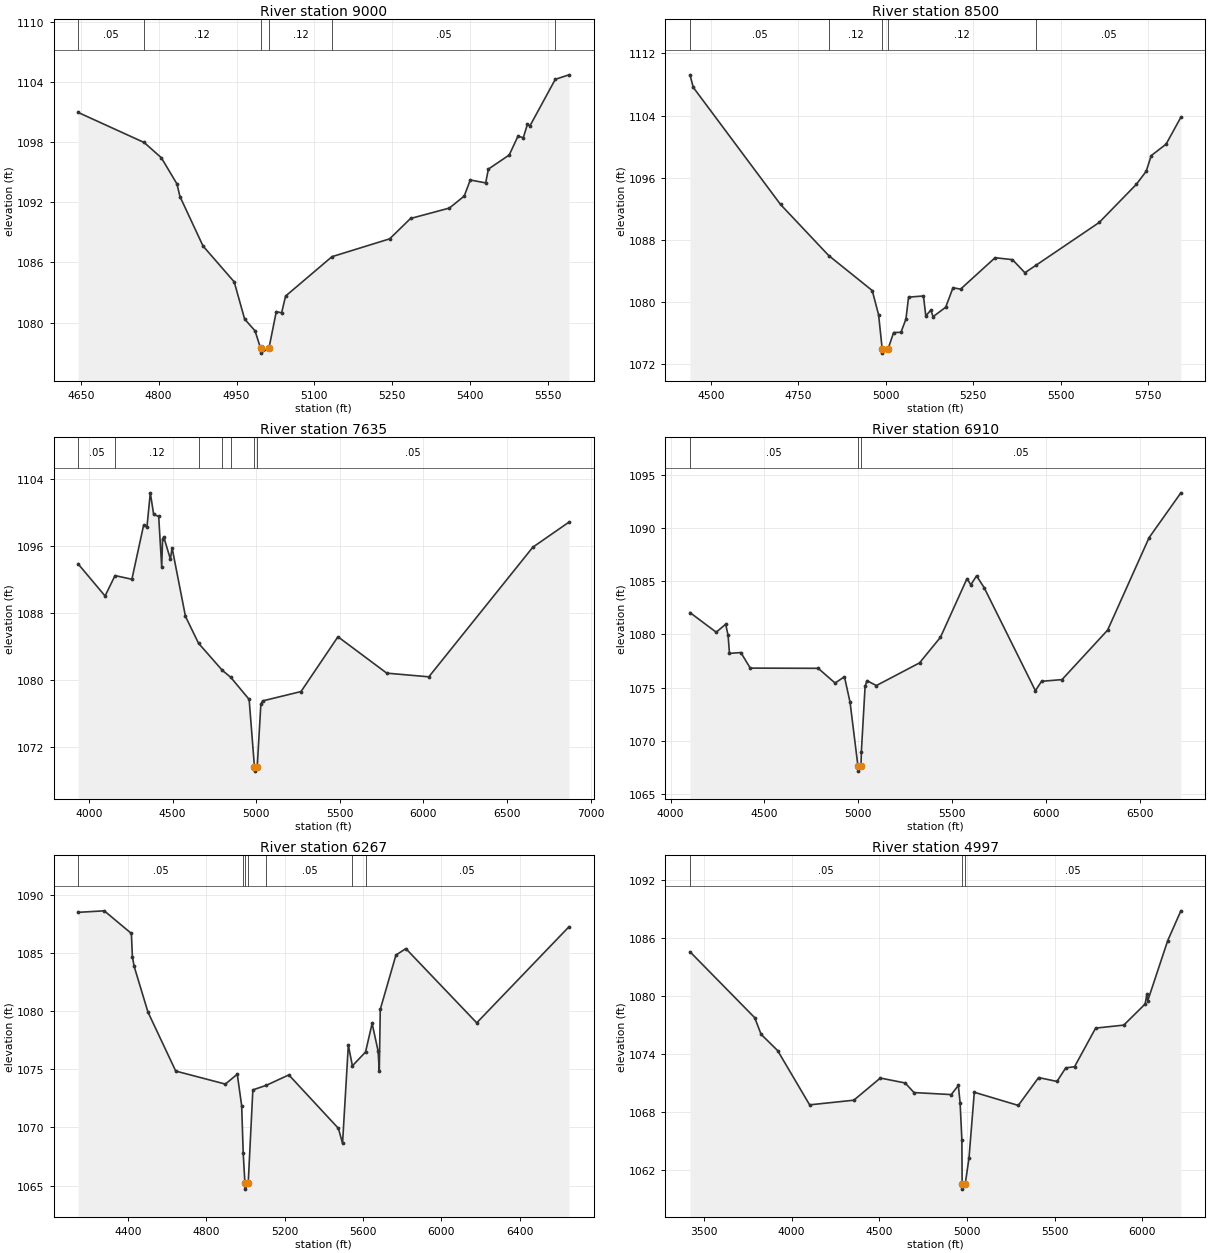
Type RM Length L Ch R = 1,9000,500,500,500
BEGIN DESCRIPTION:
BAILEY BRANCH 18.0
END DESCRIPTION:
XS GIS Cut Line= 3
      2819105.72     10221853.11      2819459.99     10221880.16
      2820030.68     10221728.11
#Sta/Elev= 30
  4644.7 1100.96  4772.0 1097.96  4805.1 1096.44  4835.2 1093.83  4841.0 1092.57
  4885.4 1087.64  4945.5 1084.06  4965.6 1080.35  4985.7 1079.17  4996.2 1077.45
  4996.7 1076.95  5012.5 1077.45  5026.6 1081.09  5036.9 1080.97  5044.5 1082.64
  5133.9 1086.57  5245.1 1088.35  5285.3 1090.38  5360.2 1091.42  5388.8 1092.62
  5400.4 1094.22  5430.1 1093.93  5435.3 1095.31  5475.4 1096.71  5492.3 1098.59
  5502.6 1098.44  5510.4 1099.76  5515.5 1099.63  5564.2 1104.26  5590.6 1104.71
#Mann=6,-1,0
  4644.7    0.05       0  4772.0    0.12       0  4996.2    0.07       0
  5012.5    0.12       0  5133.9    0.05       0  5564.2    0.12       0
Bank Sta=4996.2,5012.5
Exp/Cntr=0.3,0.1

Type RM Length L Ch R = 1,8500,865,865,865
BEGIN DESCRIPTION:
BAILEY BRANCH 17.0
END DESCRIPTION:
XS GIS Cut Line= 3
      2818905.64     10222153.10      2819425.01     10222363.59
      2820055.66     10221803.13
#Sta/Elev= 30
  4439.6 1109.25  4449.0 1107.64  4698.6 1092.58  4836.4 1086.01  4960.9 1081.51
  4979.1 1078.39  4989.5 1073.96  4990.0 1073.46  5005.9 1073.96  5022.1 1076.11
  5043.0 1076.14  5057.3 1077.83  5064.8 1080.66  5107.4 1080.81  5114.1 1078.25
  5128.3 1078.98  5135.0 1078.15  5171.0 1079.36  5191.9 1081.87  5213.6 1081.69
  5312.3 1085.73  5362.1 1085.48  5397.6 1083.80  5430.3 1084.79  5610.0 1090.26
  5716.2 1095.16  5744.6 1096.85  5758.9 1098.86  5801.5 1100.34  5843.7 1103.80
#Mann=5,-1,0
  4439.6    0.05       0  4836.4    0.12       0  4989.5    0.07       0
  5005.9    0.12       0  5430.3    0.05       0
Bank Sta=4989.5,5005.9
Exp/Cntr=0.3,0.1

Type RM Length L Ch R = 1,7635,725,725,725
BEGIN DESCRIPTION:
Mapping XS 6d2b6545
END DESCRIPTION:
XS GIS Cut Line= 5
      2818244.59     10223258.16      2819260.25     10223197.39
      2819737.68     10223214.76      2820701.22     10223058.51
      2821151.61     10222945.91
#Sta/Elev= 30
  3935.0 1093.87  4096.4 1090.03  4155.9 1092.47  4256.7 1092.03  4326.8 1098.48
  4346.8 1098.27  4366.9 1102.36  4386.9 1099.78  4417.0 1099.54  4435.1 1093.48
  4440.1 1096.79  4447.0 1097.10  4487.1 1094.44  4497.1 1095.78  4577.2 1087.59
  4655.4 1084.38  4797.8 1081.14  4847.6 1080.32  4957.9 1077.67  4989.7 1069.60
  4990.2 1069.10  5006.2 1069.60  5028.0 1077.10  5038.0 1077.49  5268.1 1078.61
  5489.0 1085.16  5780.9 1080.81  6032.5 1080.37  6654.3 1095.86  6870.6 1098.86
#Mann=7,-1,0
  3935.0    0.05       0  4155.9    0.12       0  4655.4    0.05       0
  4797.8    0.12       0  4847.6    0.05       0  4989.7    0.05       0
  5006.2    0.05       0
Bank Sta=4989.7,5006.2
Exp/Cntr=0.3,0.1

Type RM Length L Ch R = 1,6910,643,643,643
BEGIN DESCRIPTION:
Mapping XS 902f76a1
END DESCRIPTION:
XS GIS Cut Line= 4
      2818426.96     10223822.40      2818965.11     10223891.84
      2819642.20     10223909.20      2821021.53     10223692.32
#Sta/Elev= 30
  4103.0 1082.04  4242.9 1080.20  4293.3 1080.95  4306.2 1079.89  4313.5 1078.21
  4374.0 1078.29  4424.4 1076.83  4786.2 1076.81  4876.3 1075.43  4926.3 1076.02
  4956.3 1073.61  4998.0 1067.66  4998.5 1067.16  5014.6 1067.66  5016.3 1068.95
  5036.3 1075.11  5046.3 1075.65  5096.3 1075.19  5326.4 1077.32  5437.8 1079.72
  5579.5 1085.23  5599.8 1084.64  5630.1 1085.49  5670.6 1084.39  5943.9 1074.71
  5976.6 1075.59  6085.7 1075.75  6328.6 1080.39  6549.7 1089.07  6719.2 1093.28
#Mann=3,-1,0
  4103.0    0.05       0  4998.0    0.05       0  5014.6    0.05       0
Bank Sta=4998,5014.6
Exp/Cntr=0.3,0.1

Type RM Length L Ch R = 1,6267,1270,1270,1270
BEGIN DESCRIPTION:
Mapping XS 452e2a48
END DESCRIPTION:
XS GIS Cut Line= 4
      2818513.73     10224403.99      2819364.42     10224542.88
      2820301.92     10224690.45      2820996.34     10224664.41
#Sta/Elev= 30
  4144.9 1088.51  4278.6 1088.64  4417.0 1086.69  4422.1 1084.70  4430.6 1083.89
  4501.5 1079.93  4643.4 1074.85  4896.7 1073.73  4957.5 1074.58  4980.0 1071.86
  4987.8 1067.79  4996.6 1065.19  4997.1 1064.69  5013.3 1065.19  5037.0 1073.23
  5106.6 1073.63  5220.7 1074.52  5473.8 1069.92  5494.9 1068.63  5524.4 1077.07
  5545.2 1075.30  5612.3 1076.49  5645.9 1078.95  5676.3 1076.58  5682.5 1074.89
  5687.5 1080.16  5767.4 1084.83  5818.0 1085.39  6179.8 1079.00  6650.8 1087.27
#Mann=7,-1,0
  4144.9    0.05       0  4987.8    0.12       0  4996.6    0.07       0
  5013.3    0.12       0  5106.6    0.05       0  5545.2    0.12       0
  5612.3    0.05       0
Bank Sta=4996.6,5013.3
Exp/Cntr=0.3,0.1

Type RM Length L Ch R = 1,4997,1694,1694,1694
BEGIN DESCRIPTION:
Mapping XS 6701f329
END DESCRIPTION:
XS GIS Cut Line= 5
      2818617.86     10224811.96      2819416.50     10225315.45
      2820128.31     10225419.62      2821039.77     10225471.70
      2821239.37     10225376.24
#Sta/Elev= 30
  3421.3 1084.56  3790.1 1077.75  3826.6 1076.03  3920.8 1074.35  4103.2 1068.74
  4355.1 1069.22  4506.1 1071.51  4647.6 1071.00  4698.1 1070.01  4910.3 1069.80
  4950.8 1070.74  4960.9 1068.94  4971.0 1065.10  4972.4 1060.53  4972.9 1060.03
  4989.7 1060.53  5011.4 1063.23  5041.7 1070.04  5292.5 1068.68  5408.3 1071.56
  5512.9 1071.16  5562.9 1072.56  5613.0 1072.68  5733.2 1076.67  5893.5 1076.98
  6015.4 1079.16  6025.1 1080.15  6030.6 1079.52  6144.0 1085.71  6219.0 1088.79
#Mann=3,-1,0
  3421.3    0.05       0  4972.4    0.05       0  4989.7    0.05       0
Bank Sta=4972.4,4989.7
Exp/Cntr=0.3,0.1