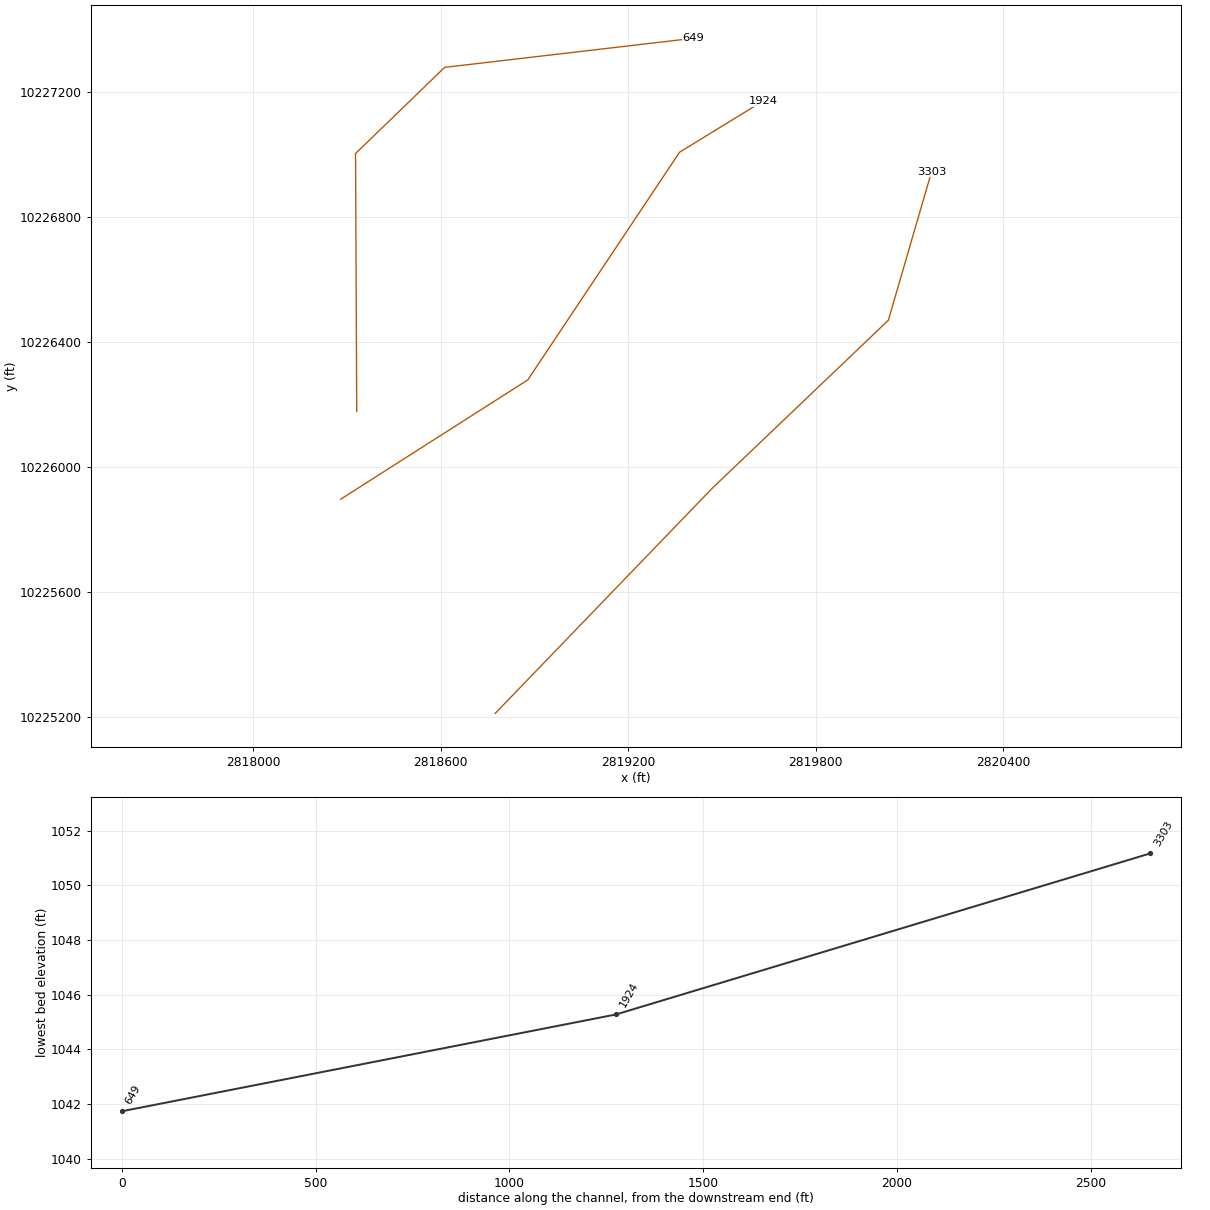
HEC-RAS study BAILEY BRANCH.prj: BAILEY BRANCH Base Level Engineering

--- BAILEY BRANCH.g01 (geometry) --- (continued)

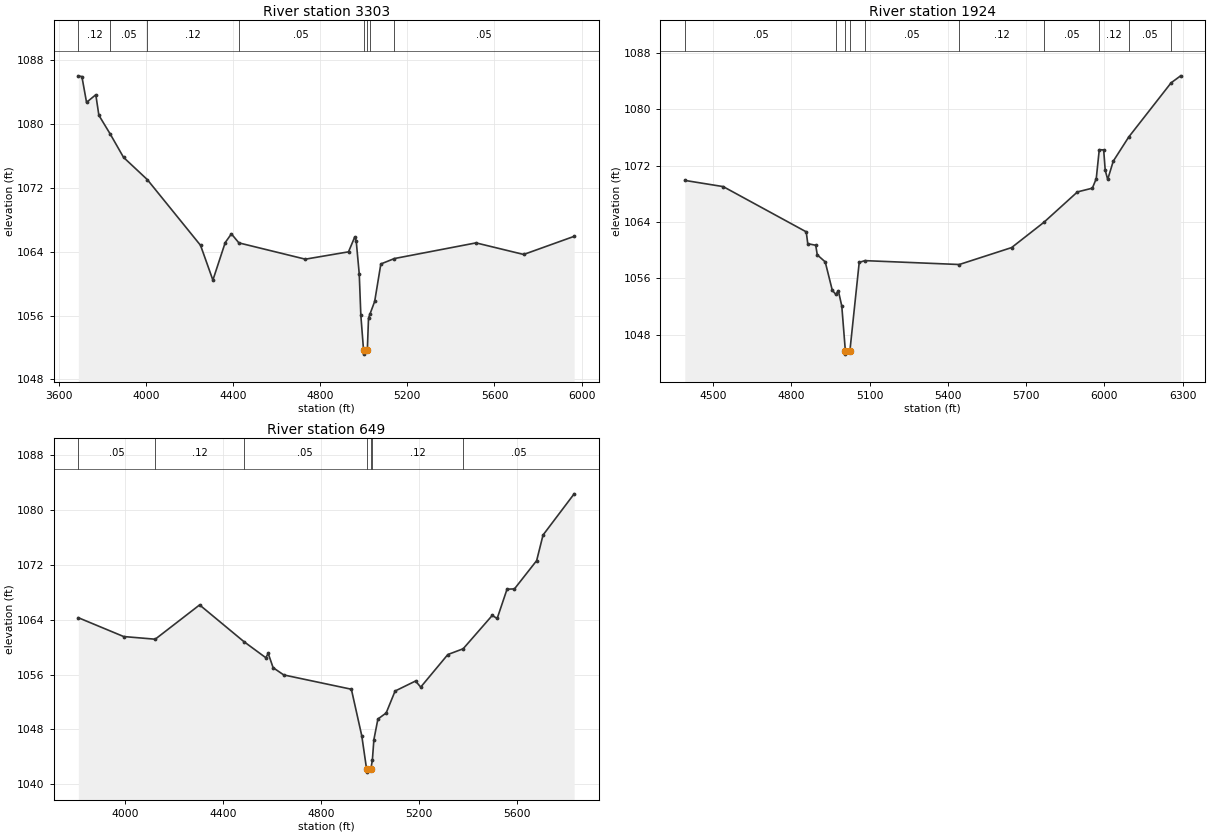
Type RM Length L Ch R = 1,3303,1379,1379,1379
BEGIN DESCRIPTION:
Mapping XS 0e574d28
END DESCRIPTION:
XS GIS Cut Line= 4
      2818774.15     10225211.30      2819468.59     10225931.77
      2820032.82     10226469.96      2820171.20     10226945.64
#Sta/Elev= 30
  3690.0 1086.02  3706.4 1085.92  3727.7 1082.70  3770.2 1083.65  3784.3 1081.08
  3837.3 1078.69  3897.5 1075.81  4006.4 1073.03  4251.0 1064.79  4307.6 1060.44
  4364.2 1065.14  4392.5 1066.23  4427.0 1065.10  4731.9 1063.06  4930.1 1063.98
  4958.4 1065.82  4965.3 1065.39  4979.4 1061.20  4986.7 1056.03  4999.1 1051.67
  4999.6 1051.17  5016.5 1051.67  5021.9 1055.66  5028.5 1056.18  5050.2 1057.77
  5078.5 1062.46  5140.8 1063.14  5515.3 1065.10  5734.1 1063.65  5965.8 1065.92
#Mann=8,-1,0
  3690.0    0.12       0  3837.3    0.05       0  4006.4    0.12       0
  4427.0    0.05       0  4999.1    0.05       0  5016.5    0.05       0
  5028.5    0.12       0  5140.8    0.05       0
Bank Sta=4999.1,5016.5
Exp/Cntr=0.3,0.1

Type RM Length L Ch R = 1,1924,1275,1275,1275
BEGIN DESCRIPTION:
Mapping XS 5a9e536d
END DESCRIPTION:
XS GIS Cut Line= 4
      2818279.37     10225897.06      2818878.31     10226278.99
      2819364.42     10227008.16      2819632.13     10227172.24
#Sta/Elev= 30
  4391.3 1069.90  4538.6 1069.02  4856.8 1062.61  4862.7 1060.93  4893.2 1060.71
  4899.1 1059.35  4929.6 1058.35  4956.7 1054.33  4970.3 1053.74  4979.9 1054.27
  4993.1 1052.09  5006.7 1045.78  5007.2 1045.28  5024.3 1045.78  5059.9 1058.28
  5081.6 1058.53  5443.5 1057.98  5644.1 1060.38  5767.2 1063.94  5896.5 1068.27
  5953.6 1068.80  5968.6 1070.15  5980.1 1074.25  5997.1 1074.22  6002.9 1071.33
  6012.5 1070.04  6033.8 1072.63  6092.9 1076.04  6255.5 1083.73  6292.0 1084.72
#Mann=10,-1,0
  4391.3    0.05       0  4970.3    0.12       0  5006.7    0.07       0
  5024.3    0.12       0  5081.6    0.05       0  5443.5    0.12       0
  5767.2    0.05       0  5980.1    0.12       0  6092.9    0.05       0
  6255.5    0.12       0
Bank Sta=5006.7,5024.3
Exp/Cntr=0.3,0.1

Type RM Length L Ch R = 1,649,0,0,0
BEGIN DESCRIPTION:
BAILEY BRANCH 16.0
END DESCRIPTION:
XS GIS Cut Line= 4
      2818330.68     10226178.10      2818326.89     10227003.88
      2818612.22     10227279.82      2819407.78     10227372.74
#Sta/Elev= 30
  3810.4 1064.30  3995.4 1061.55  4124.2 1061.16  4305.4 1066.17  4486.1 1060.81
  4575.4 1058.46  4585.4 1059.08  4605.4 1057.00  4648.8 1055.94  4924.8 1053.85
  4967.3 1047.04  4986.7 1042.24  4987.2 1041.74  5004.4 1042.24  5010.4 1043.45
  5016.7 1046.48  5033.1 1049.50  5066.8 1050.38  5103.3 1053.59  5186.7 1055.05
  5207.8 1054.16  5318.5 1058.92  5381.0 1059.76  5499.7 1064.63  5519.9 1064.19
  5560.2 1068.47  5590.4 1068.51  5681.0 1072.64  5707.1 1076.38  5834.1 1082.40
#Mann=7,-1,0
  3810.4    0.05       0  4124.2    0.12       0  4486.1    0.05       0
  4986.7    0.05       0  5004.4    0.05       0  5010.4    0.12       0
  5381.0    0.05       0
Bank Sta=4986.7,5004.4
Exp/Cntr=0.3,0.1

Chan Stop Cuts=-1