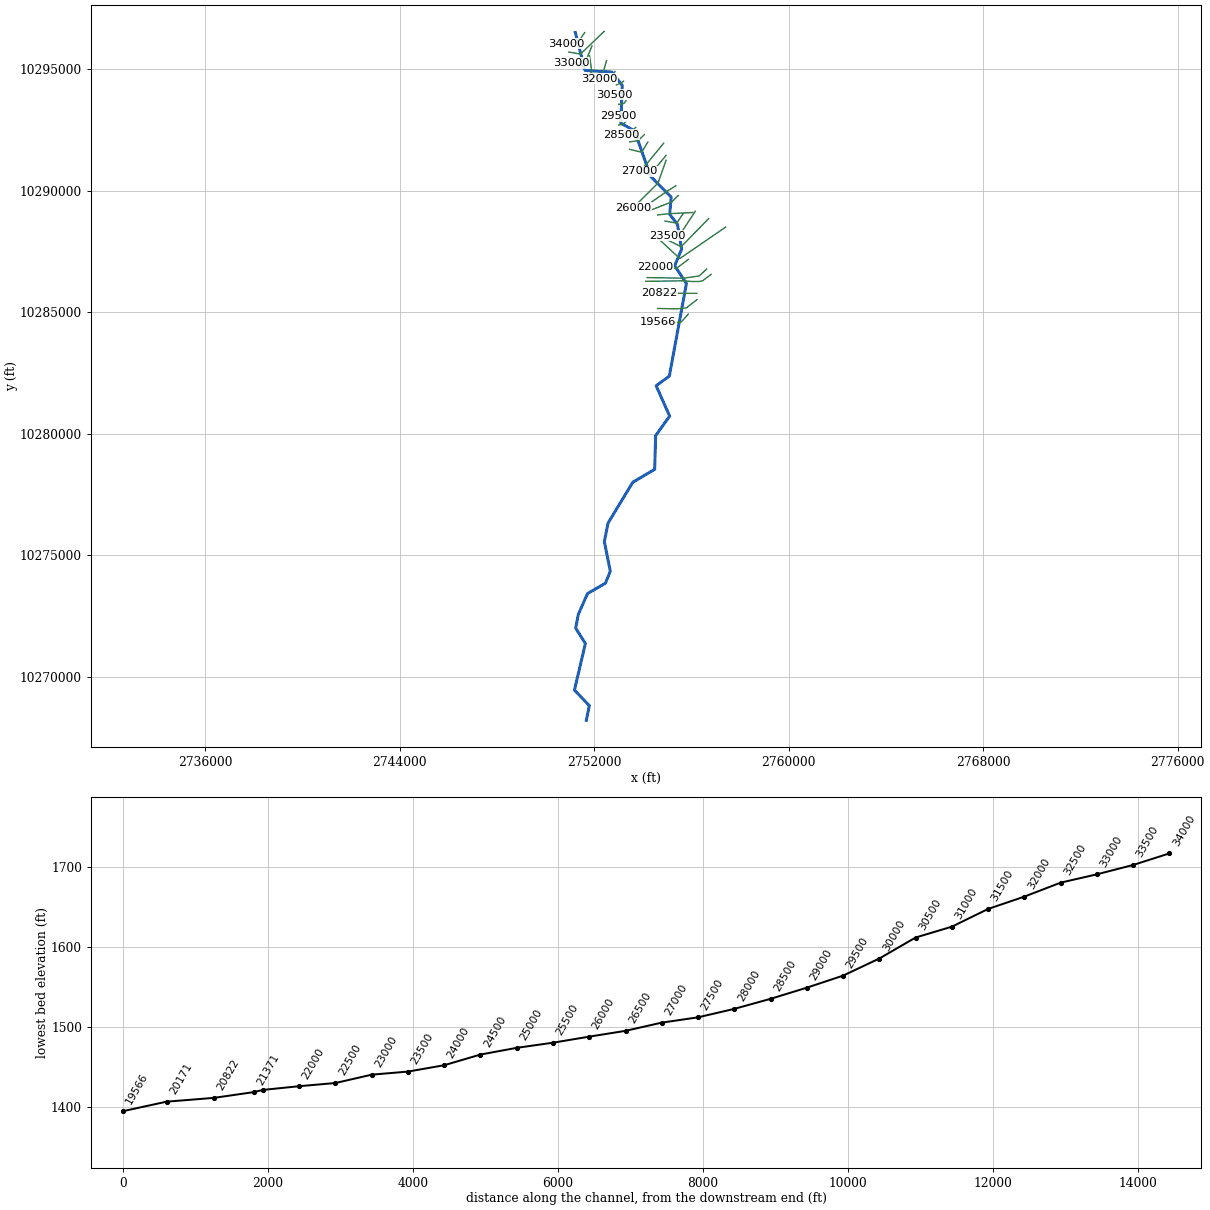
--- BAUMANN CREEK.prj (project) ---

Proj Title=BAUMANN CREEK Base Level Engineering
Current Plan=p01
Default Exp/Contr=0.3,0.1
English Units
Geom File=g01
Flow File=f01
Plan File=p01
BEGIN DESCRIPTION:
BAUMANN CREEK
END DESCRIPTION:

--- BAUMANN CREEK.p01 (plan) ---

Plan Title=Multiple Run
Short Identifier=Multiple
Geom File=g01
Flow File=f01
Subcritical Flow
K Sum by GR= 0
Std Step Tol= 0.01
Critical Tol= 0.01
Num of Std Step Trials= 20
Max Error Tol= 0.3
Flow Tol Ratio= 0.001
Split Flow NTrial= 30
Split Flow Tol= 0.02
Split Flow Ratio= 0.02
Log Output Level= 0
Friction Slope Method= 1
Unsteady Friction Slope Method= 2
Unsteady Bridges Friction Slope Method= 1
Parabolic Critical Depth
Global Vel Dist=  1 , 1 , 1
Global Log Level= 0
CheckData=True
Encroach Param= -1, 0, 0, 0
BEGIN DESCRIPTION:
Multiple Run
END DESCRIPTION:

--- BAUMANN CREEK.f01 (steady flow) ---

Flow Title=Multiple
Number of Profiles=7
Profile Names=10-year,25-year,50-year,1pct_min,100-year,1pct_plu,500-year
River Rch & RM= BAUMANN CREEK,Reach-1,34000
     486     797     928     742    1224    2019    1663
River Rch & RM= BAUMANN CREEK,Reach-1,26000
     800    1354    2952    2477    4267    7350    6244
River Rch & RM= BAUMANN CREEK,Reach-1,18500
    1041    1780    4207    2549    6153   14852    8976
River Rch & RM= BAUMANN CREEK,Reach-1,17737
    1182    2041    4736    3578    6943   13473   10109
River Rch & RM= BAUMANN CREEK,Reach-1,15000
    1408    2462    5657    4128    8330   16812   12100
River Rch & RM= BAUMANN CREEK,Reach-1,11000
    1531    2693    6145    4514    9066   18207   13152
River Rch & RM= BAUMANN CREEK,Reach-1,9000
    1715    3039    6951    5968   10288   17735   14900
River Rch & RM= BAUMANN CREEK,Reach-1,6500
    1946    3489    7598    5592   11248   22625   16240
River Rch & RM= BAUMANN CREEK,Reach-1,412
    2072    3726    8230    6138   12215   24309   17622
Boundary for River Rch & Prof#=BAUMANN CREEK,Reach-1,1
Up Type=0
Dn Type=3
Dn Slope=0.005
Boundary for River Rch & Prof#=BAUMANN CREEK,Reach-1,2
Up Type=0
Dn Type=3
Dn Slope=0.005
Boundary for River Rch & Prof#=BAUMANN CREEK,Reach-1,3
Up Type=0
Dn Type=3
Dn Slope=0.005
Boundary for River Rch & Prof#=BAUMANN CREEK,Reach-1,4
Up Type=0
Dn Type=3
Dn Slope=0.005
Boundary for River Rch & Prof#=BAUMANN CREEK,Reach-1,5
Up Type=0
Dn Type=3
Dn Slope=0.005
Boundary for River Rch & Prof#=BAUMANN CREEK,Reach-1,6
Up Type=0
Dn Type=3
Dn Slope=0.005
Boundary for River Rch & Prof#=BAUMANN CREEK,Reach-1,7
Up Type=0
Dn Type=3
Dn Slope=0.005

--- BAUMANN CREEK.g01 (geometry) ---

Geom Title=Existing Conditions

River Reach=BAUMANN CREEK,Reach-1
Reach XY= 30
      2751220.25     10296505.00      2751621.75     10294948.00
      2752720.25     10294881.00      2753152.25     10294333.00
      2753093.25     10292776.00      2753661.75     10292460.00
      2754314.50     10290592.00      2755163.50     10289738.00
      2755103.50     10289029.00      2755424.00     10288615.00
      2755591.25     10287589.00      2755308.25     10286912.00
      2755791.00     10286184.00      2755088.25     10282373.00
      2754545.75     10281976.00      2755101.25     10280729.00
      2754526.25     10279926.00      2754484.50     10278536.00
      2753587.25     10278010.00      2752567.25     10276328.00
      2752415.75     10275565.00      2752661.25     10274348.00
      2752456.75     10273851.00      2751723.50     10273429.00
      2751344.75     10272575.00      2751235.50     10272007.00
      2751635.50     10271374.00      2751185.50     10269457.00
      2751798.50     10268818.00      2751673.00     10268214.00

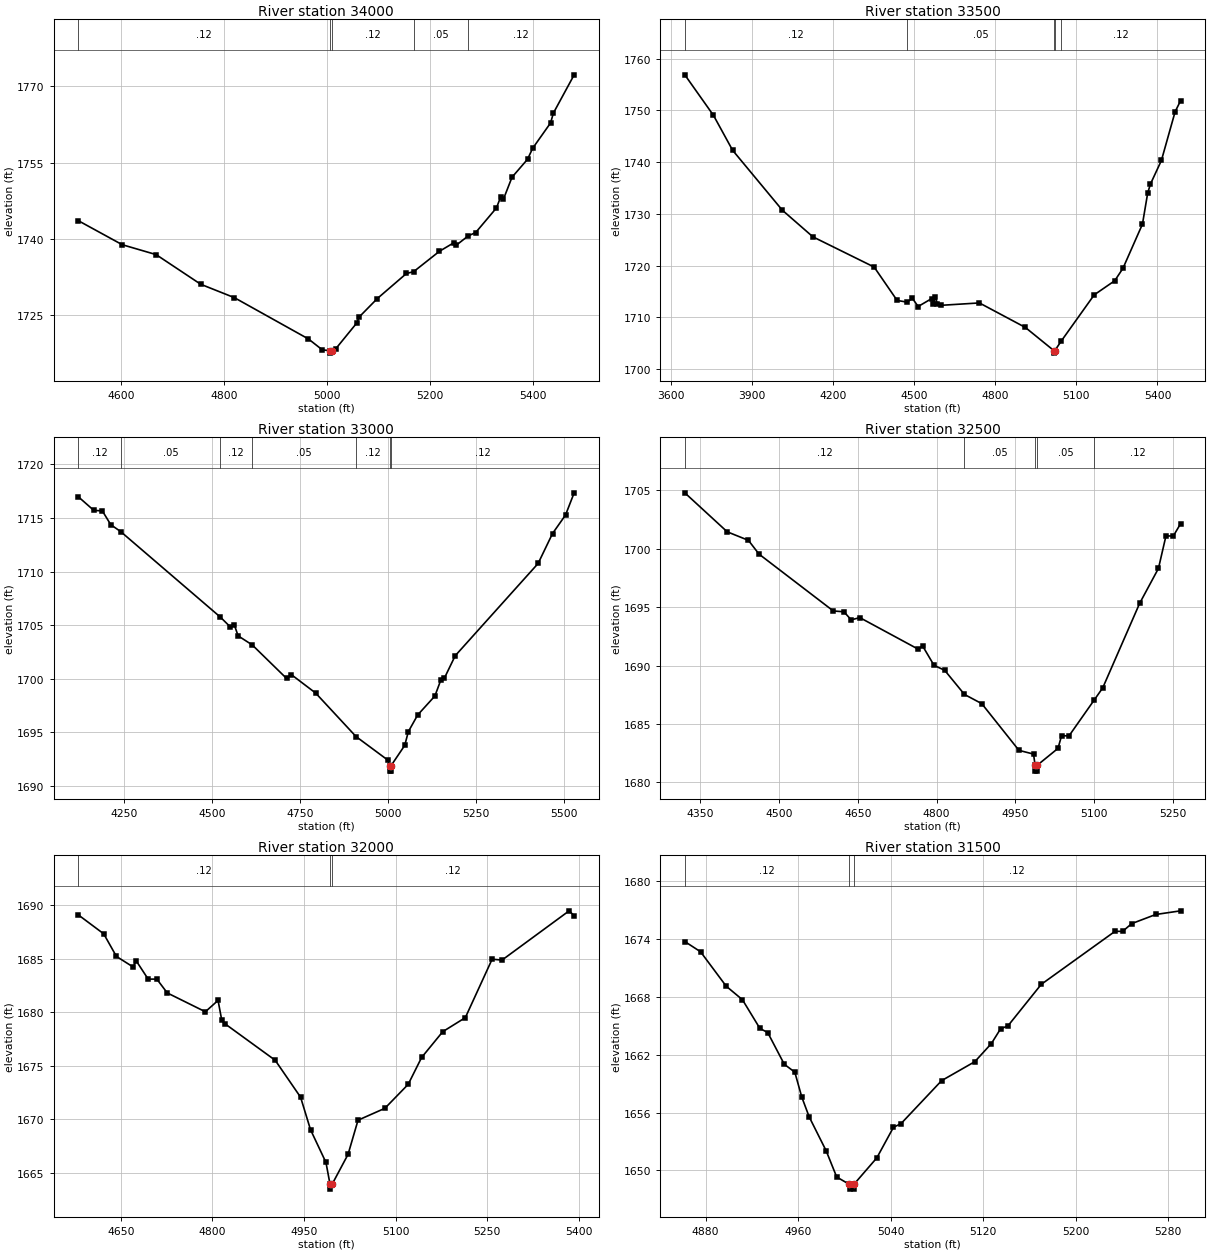
Type RM Length L Ch R = 1,34000,500,500,500
BEGIN DESCRIPTION:
BAUMANN CREEK 68.0
END DESCRIPTION:
XS GIS Cut Line= 3
      2751605.70     10296503.14      2751333.24     10296104.93
      2750855.64     10296053.11
#Sta/Elev= 30
  4517.5 1743.59  4602.8 1738.87  4668.5 1736.93  4755.2 1731.10  4820.5 1728.47
  4964.4 1720.35  4991.5 1718.20  5005.6 1718.07  5005.8 1717.57  5009.6 1718.07
  5017.7 1718.46  5057.9 1723.45  5063.1 1724.69  5098.1 1728.29  5154.7 1733.22
  5168.6 1733.57  5218.8 1737.58  5246.3 1739.23  5251.3 1738.76  5274.6 1740.60
  5289.2 1741.27  5329.5 1746.10  5337.9 1748.32  5342.9 1747.77  5359.7 1752.13
  5389.8 1755.65  5399.9 1757.83  5434.6 1762.80  5440.1 1764.74  5480.4 1772.25
#Mann=5,-1,0
  4517.5    0.12       0  5005.6    0.07       0  5009.6    0.12       0
  5168.6    0.05       0  5274.6    0.12       0
Bank Sta=5005.6,5009.6
Exp/Cntr=0.3,0.1

Type RM Length L Ch R = 1,33500,500,500,500
BEGIN DESCRIPTION:
BAUMANN CREEK 67.0
END DESCRIPTION:
XS GIS Cut Line= 3
      2752405.66     10296553.09      2751434.16     10295619.45
      2750955.72     10295703.11
#Sta/Elev= 30
  3652.6 1756.87  3758.7 1749.03  3829.4 1742.29  4013.2 1730.71  4126.3 1725.56
  4352.7 1719.72  4437.6 1713.27  4474.1 1712.95  4494.2 1713.67  4515.3 1712.10
  4565.0 1713.62  4571.9 1712.51  4579.1 1714.02  4586.1 1712.62  4600.2 1712.33
  4741.7 1712.79  4911.5 1708.06  5016.8 1703.59  5017.0 1703.09  5020.8 1703.59
  5044.6 1705.44  5166.2 1714.35  5242.1 1717.08  5272.5 1719.48  5344.6 1728.02
  5363.9 1734.02  5374.1 1735.76  5414.7 1740.33  5465.4 1749.75  5485.7 1751.88
#Mann=5,-1,0
  3652.6    0.12       0  4474.1    0.05       0  5016.8    0.05       0
  5020.8    0.05       0  5044.6    0.12       0
Bank Sta=5016.8,5020.8
Exp/Cntr=0.3,0.1

Type RM Length L Ch R = 1,33000,500,500,500
BEGIN DESCRIPTION:
BAUMANN CREEK 66.0
END DESCRIPTION:
XS GIS Cut Line= 3
      2751905.67     10295953.08      2751572.66     10295139.71
      2751055.65     10295253.12
#Sta/Elev= 30
  4121.1 1716.98  4165.2 1715.71  4189.2 1715.67  4213.2 1714.38  4241.2 1713.74
  4524.7 1705.75  4552.2 1704.86  4564.1 1705.03  4574.9 1704.01  4615.1 1703.16
  4712.4 1700.04  4726.2 1700.39  4795.2 1698.67  4909.6 1694.62  5000.0 1692.42
  5005.1 1691.89  5005.4 1691.39  5008.9 1691.39  5009.1 1691.89  5048.1 1693.79
  5058.3 1695.07  5084.9 1696.63  5133.8 1698.40  5150.5 1699.88  5160.7 1700.06
  5191.4 1702.15  5426.9 1710.76  5467.8 1713.55  5504.8 1715.28  5529.3 1717.35
#Mann=7,-1,0
  4121.1    0.12       0  4241.2    0.05       0  4524.7    0.12       0
  4615.1    0.05       0  4909.6    0.12       0  5005.1    0.07       0
  5009.1    0.12       0
Bank Sta=5005.1,5009.1
Exp/Cntr=0.3,0.1

Type RM Length L Ch R = 1,32500,500,500,500
BEGIN DESCRIPTION:
BAUMANN CREEK 65.0
END DESCRIPTION:
XS GIS Cut Line= 3
      2751805.69     10295553.08      2751902.51     10294880.41
      2751705.69     10294703.11
#Sta/Elev= 30
  4320.4 1704.80  4401.2 1701.46  4441.6 1700.73  4461.8 1699.55  4603.3 1694.68
  4623.5 1694.61  4637.4 1693.92  4653.8 1694.11  4764.9 1691.41  4773.3 1691.69
  4795.2 1690.02  4815.4 1689.60  4853.1 1687.53  4886.1 1686.74  4956.9 1682.74
  4984.7 1682.42  4987.7 1681.46  4988.0 1680.96  4991.5 1680.96  4991.7 1681.46
  5031.3 1682.91  5038.1 1683.99  5052.3 1683.98  5100.7 1687.08  5116.5 1688.09
  5186.8 1695.33  5222.7 1698.33  5236.9 1701.10  5251.1 1701.11  5264.9 1702.16
#Mann=5,-1,0
  4320.4    0.12       0  4853.1    0.05       0  4987.7    0.05       0
  4991.7    0.05       0  5100.7    0.12       0
Bank Sta=4987.7,4991.7
Exp/Cntr=0.3,0.1

Type RM Length L Ch R = 1,32000,500,500,500
BEGIN DESCRIPTION:
BAUMANN CREEK 64.0
END DESCRIPTION:
XS GIS Cut Line= 3
      2752505.69     10295353.13      2752390.04     10294949.58
      2752205.66     10294603.08
#Sta/Elev= 30
  4580.2 1689.10  4621.8 1687.33  4642.6 1685.22  4669.8 1684.24  4675.0 1684.81
  4694.6 1683.10  4708.8 1683.10  4725.9 1681.81  4788.3 1680.05  4809.1 1681.11
  4815.2 1679.25  4820.4 1678.93  4902.7 1675.52  4944.3 1672.07  4960.6 1669.03
  4985.9 1665.97  4992.4 1663.98  4992.6 1663.48  4996.4 1663.98  5022.1 1666.73
  5038.4 1669.92  5082.4 1671.03  5120.6 1673.27  5142.6 1675.78  5177.2 1678.19
  5214.2 1679.50  5258.1 1684.96  5274.4 1684.88  5384.3 1689.48  5392.5 1689.02
#Mann=3,-1,0
  4580.2    0.12       0  4992.4    0.07       0  4996.4    0.12       0
Bank Sta=4992.4,4996.4
Exp/Cntr=0.3,0.1

Type RM Length L Ch R = 1,31500,500,500,500
BEGIN DESCRIPTION:
BAUMANN CREEK 63.0
END DESCRIPTION:
XS GIS Cut Line= 3
      2752855.70     10294903.14      2752780.30     10294787.55
      2752555.72     10294603.14
#Sta/Elev= 30
  4862.0 1673.76  4875.6 1672.70  4897.8 1669.12  4911.8 1667.72  4926.9 1664.74
  4933.7 1664.30  4948.0 1661.01  4957.1 1660.19  4963.1 1657.61  4969.5 1655.55
  4984.2 1652.02  4993.3 1649.30  5004.2 1648.54  5004.5 1648.04  5008.0 1648.04
  5008.2 1648.54  5028.0 1651.29  5042.4 1654.47  5048.8 1654.83  5084.0 1659.31
  5112.7 1661.28  5127.0 1663.16  5134.9 1664.68  5141.4 1665.01  5170.1 1669.31
  5234.0 1674.83  5240.4 1674.81  5248.3 1675.62  5269.1 1676.57  5290.6 1676.95
#Mann=3,-1,0
  4862.0    0.12       0  5004.2    0.07       0  5008.2    0.12       0
Bank Sta=5004.2,5008.2
Exp/Cntr=0.3,0.1

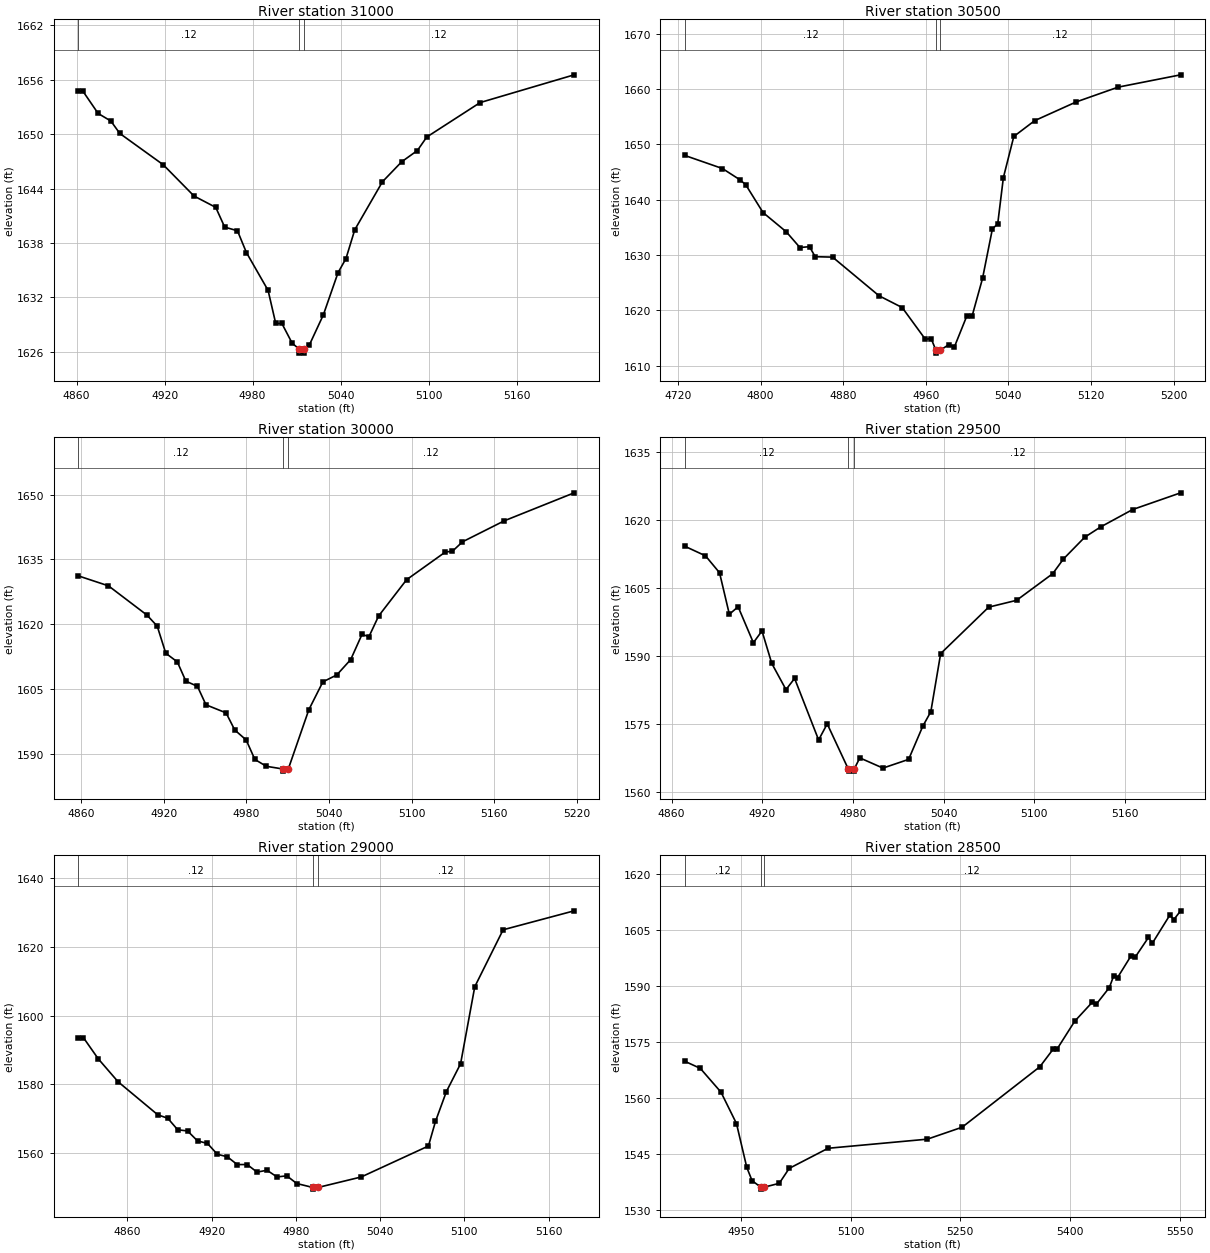
Type RM Length L Ch R = 1,31000,500,500,500
BEGIN DESCRIPTION:
BAUMANN CREEK 62.0
END DESCRIPTION:
XS GIS Cut Line= 3
      2753205.71     10294503.13      2753092.20     10294423.24
      2752905.65     10294353.10
#Sta/Elev= 30
  4861.2 1654.74  4864.3 1654.74  4874.7 1652.28  4883.4 1651.44  4889.5 1650.07
  4919.1 1646.62  4940.1 1643.17  4954.9 1641.92  4961.0 1639.74  4969.7 1639.34
  4975.8 1636.94  4990.6 1632.76  4995.8 1629.11  5000.0 1629.11  5007.0 1626.94
  5011.4 1626.34  5011.7 1625.84  5015.2 1625.84  5015.4 1626.34  5018.8 1626.76
  5028.3 1630.07  5038.3 1634.72  5043.7 1636.27  5049.7 1639.45  5068.6 1644.75
  5081.7 1646.95  5092.4 1648.19  5098.8 1649.68  5135.2 1653.48  5199.3 1656.54
#Mann=3,-1,0
  4861.2    0.12       0  5011.4    0.07       0  5015.4    0.12       0
Bank Sta=5011.4,5015.4
Exp/Cntr=0.3,0.1

Type RM Length L Ch R = 1,30500,500,500,500
BEGIN DESCRIPTION:
BAUMANN CREEK 61.0
END DESCRIPTION:
XS GIS Cut Line= 3
      2753255.71     10294103.13      2753010.50     10293982.22
      2752805.66     10293953.11
#Sta/Elev= 30
  4726.6 1648.02  4763.1 1645.65  4780.0 1643.62  4785.6 1642.73  4802.4 1637.69
  4824.9 1634.21  4838.1 1631.37  4847.4 1631.52  4852.9 1629.71  4869.8 1629.63
  4914.7 1622.65  4937.2 1620.51  4959.6 1614.78  4965.2 1614.91  4969.9 1612.77
  4970.2 1612.27  4973.9 1612.77  4982.1 1613.78  4987.7 1613.37  4999.9 1619.04
  5005.0 1619.04  5015.0 1625.77  5024.6 1634.77  5029.7 1635.62  5035.2 1644.01
  5045.3 1651.45  5065.5 1654.31  5105.9 1657.71  5146.3 1660.37  5206.9 1662.60
#Mann=3,-1,0
  4726.6    0.12       0  4969.9    0.07       0  4973.9    0.12       0
Bank Sta=4969.9,4973.9
Exp/Cntr=0.3,0.1

Type RM Length L Ch R = 1,30000,500,500,500
BEGIN DESCRIPTION:
BAUMANN CREEK 60.0
END DESCRIPTION:
XS GIS Cut Line= 3
      2753305.66     10293703.08      2753220.66     10293589.21
      2753005.67     10293553.11
#Sta/Elev= 30
  4857.9 1631.19  4879.8 1628.88  4907.8 1622.10  4915.2 1619.55  4921.4 1613.29
  4929.8 1611.28  4936.0 1606.82  4944.4 1605.63  4950.6 1601.35  4965.2 1599.48
  4971.5 1595.52  4979.8 1593.21  4986.1 1588.71  4994.4 1587.12  5006.4 1586.50
  5006.6 1586.00  5010.4 1586.50  5025.3 1600.21  5035.5 1606.66  5045.6 1608.26
  5055.7 1611.81  5063.9 1617.63  5069.0 1617.14  5076.0 1621.91  5096.3 1630.30
  5124.5 1636.72  5129.6 1636.89  5136.9 1639.07  5167.3 1643.94  5218.0 1650.41
#Mann=3,-1,0
  4857.9    0.12       0  5006.4    0.07       0  5010.4    0.12       0
Bank Sta=5006.4,5010.4
Exp/Cntr=0.3,0.1

Type RM Length L Ch R = 1,29500,500,500,500
BEGIN DESCRIPTION:
BAUMANN CREEK 59.0
END DESCRIPTION:
XS GIS Cut Line= 3
      2753305.69     10293053.11      2753191.65     10293118.18
      2753005.70     10293053.12
#Sta/Elev= 30
  4868.7 1614.15  4882.4 1612.04  4891.7 1608.31  4898.2 1599.15  4904.0 1600.81
  4914.1 1592.88  4919.8 1595.47  4926.3 1588.30  4935.7 1582.54  4941.4 1585.00
  4957.3 1571.44  4963.0 1574.98  4976.9 1565.06  4977.1 1564.56  4980.6 1564.56
  4980.9 1565.06  4984.6 1567.48  4999.9 1565.23  5016.9 1567.15  5026.3 1574.48
  5031.6 1577.66  5038.1 1590.47  5069.9 1600.72  5088.4 1602.23  5112.3 1608.10
  5119.4 1611.34  5133.5 1616.14  5144.0 1618.40  5165.2 1622.24  5197.0 1625.93
#Mann=3,-1,0
  4868.7    0.12       0  4976.9    0.07       0  4980.9    0.12       0
Bank Sta=4976.9,4980.9
Exp/Cntr=0.3,0.1

Type RM Length L Ch R = 1,29000,500,500,500
BEGIN DESCRIPTION:
BAUMANN CREEK 58.0
END DESCRIPTION:
XS GIS Cut Line= 3
      2753305.72     10292853.14      2753181.93     10292729.44
      2753005.68     10292703.11
#Sta/Elev= 30
  4825.0 1593.60  4828.6 1593.60  4839.2 1587.42  4853.3 1580.75  4881.6 1571.12
  4888.7 1570.12  4895.8 1566.76  4902.8 1566.42  4909.9 1563.53  4917.0 1562.78
  4924.0 1559.63  4931.1 1558.91  4938.2 1556.63  4945.3 1556.64  4952.3 1554.43
  4959.4 1554.98  4966.5 1553.03  4973.5 1553.35  4980.6 1551.11  4991.9 1549.98
  4992.1 1549.48  4995.9 1549.98  5026.5 1553.02  5074.4 1562.04  5079.4 1569.18
  5087.2 1577.90  5097.3 1585.99  5107.4 1608.42  5127.6 1625.00  5178.2 1630.52
#Mann=3,-1,0
  4825.0    0.12       0  4991.9    0.07       0  4995.9    0.12       0
Bank Sta=4991.9,4995.9
Exp/Cntr=0.3,0.1

Type RM Length L Ch R = 1,28500,500,500,500
BEGIN DESCRIPTION:
BAUMANN CREEK 57.0
END DESCRIPTION:
XS GIS Cut Line= 3
      2753705.69     10292603.12      2753614.95     10292514.40
      2753105.65     10292303.10
#Sta/Elev= 30
  4873.1 1569.76  4894.3 1567.86  4922.6 1561.49  4943.8 1553.08  4957.9 1541.34
  4965.1 1537.80  4977.2 1536.02  4977.4 1535.52  4981.2 1536.02  5002.3 1537.07
  5015.9 1541.07  5069.1 1546.46  5204.9 1548.90  5252.5 1552.10  5358.8 1568.29
  5377.2 1573.05  5382.6 1573.10  5406.5 1580.48  5430.4 1585.54  5435.8 1584.99
  5453.9 1589.50  5459.7 1592.58  5465.1 1592.16  5483.6 1598.01  5489.0 1597.57
  5507.4 1602.92  5512.8 1601.40  5536.7 1608.92  5542.1 1607.70  5551.4 1610.05
#Mann=3,-1,0
  4873.1    0.12       0  4977.2    0.07       0  4981.2    0.12       0
Bank Sta=4977.2,4981.2
Exp/Cntr=0.3,0.1

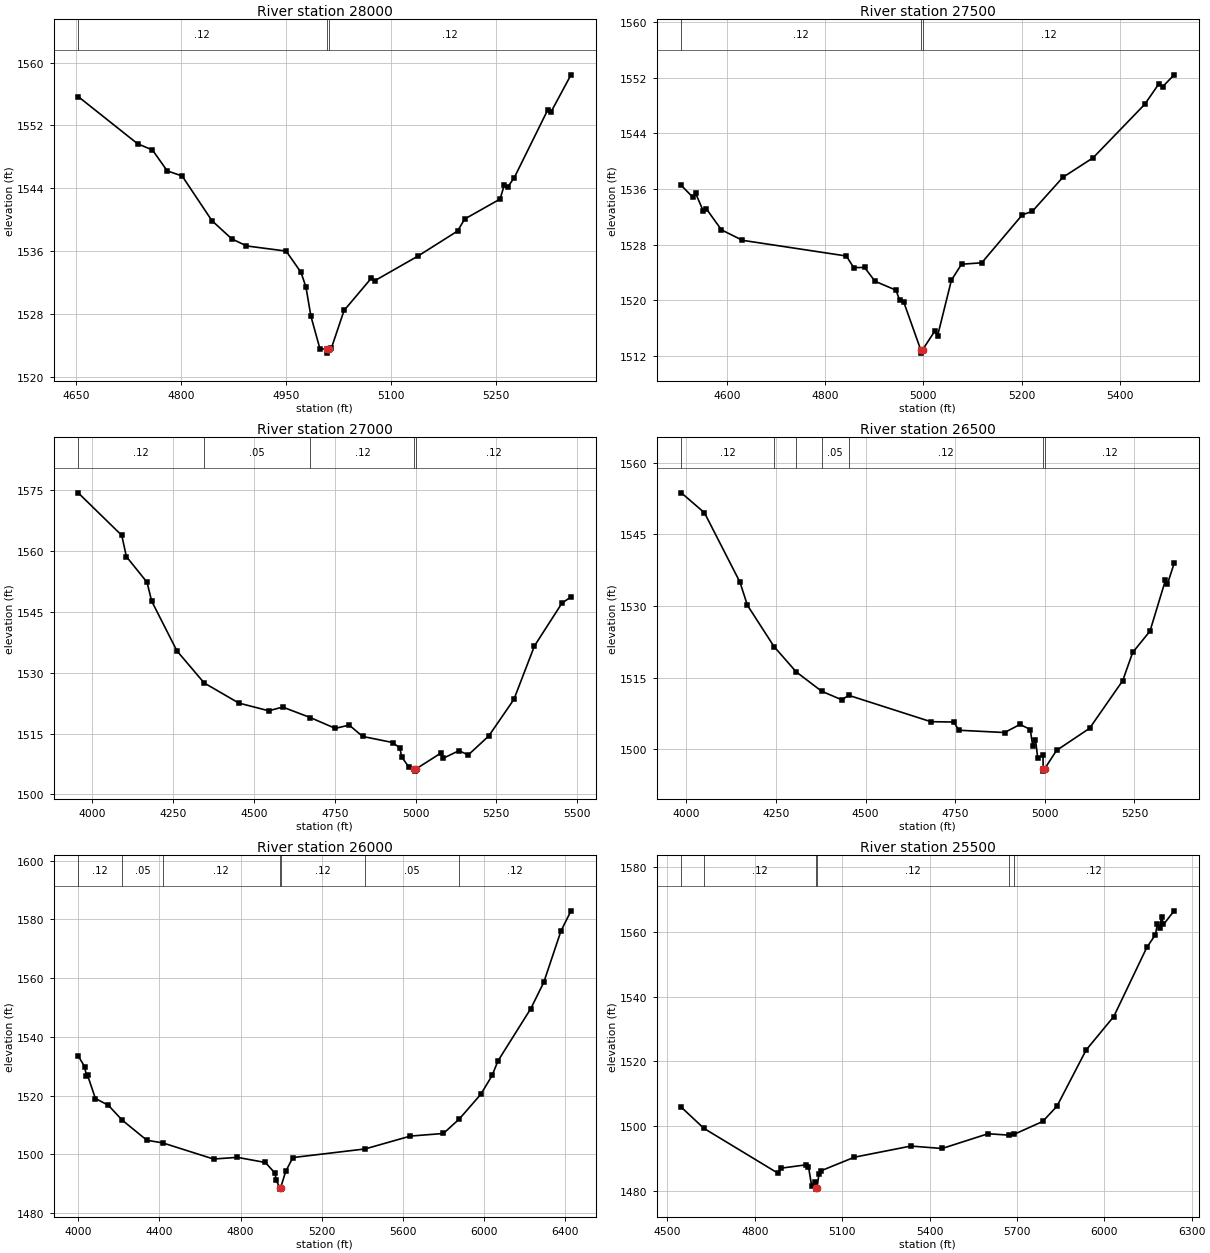
Type RM Length L Ch R = 1,28000,500,500,500
BEGIN DESCRIPTION:
BAUMANN CREEK 56.0
END DESCRIPTION:
XS GIS Cut Line= 3
      2754055.69     10292303.12      2753807.84     10292059.97
      2753455.70     10292003.11
#Sta/Elev= 30
  4652.8 1555.67  4737.6 1549.66  4758.9 1548.86  4780.0 1546.20  4801.3 1545.55
  4843.8 1539.86  4872.0 1537.55  4893.2 1536.64  4949.8 1535.98  4971.0 1533.28
  4978.1 1531.41  4985.2 1527.69  4998.0 1523.56  5007.5 1523.48  5007.7 1522.98
  5011.5 1523.48  5014.5 1523.63  5032.6 1528.42  5071.2 1532.50  5076.3 1532.20
  5138.0 1535.34  5194.6 1538.53  5204.9 1540.07  5255.4 1542.61  5261.6 1544.46
  5266.6 1544.18  5275.7 1545.34  5323.3 1553.94  5328.4 1553.75  5356.7 1558.44
#Mann=3,-1,0
  4652.8    0.12       0  5007.5    0.07       0  5011.5    0.12       0
Bank Sta=5007.5,5011.5
Exp/Cntr=0.3,0.1

Type RM Length L Ch R = 1,27500,500,500,500
BEGIN DESCRIPTION:
BAUMANN CREEK 55.0
END DESCRIPTION:
XS GIS Cut Line= 3
      2754205.69     10292003.13      2753950.91     10291581.88
      2753455.64     10291703.12
#Sta/Elev= 30
  4507.7 1536.50  4531.0 1534.82  4536.8 1535.36  4552.3 1532.83  4558.2 1533.18
  4589.2 1530.12  4631.9 1528.61  4843.3 1526.35  4858.3 1524.67  4880.2 1524.71
  4901.5 1522.72  4944.2 1521.43  4951.8 1519.96  4959.7 1519.78  4994.4 1512.87
  4994.6 1512.37  4998.4 1512.87  5023.5 1515.58  5028.7 1514.82  5056.9 1522.87
  5077.5 1525.17  5118.6 1525.37  5201.0 1532.27  5221.6 1532.79  5283.5 1537.67
  5345.1 1540.49  5450.0 1548.18  5479.0 1551.15  5486.5 1550.72  5509.9 1552.43
#Mann=3,-1,0
  4507.7    0.12       0  4994.4    0.07       0  4998.4    0.12       0
Bank Sta=4994.4,4998.4
Exp/Cntr=0.3,0.1

Type RM Length L Ch R = 1,27000,500,500,500
BEGIN DESCRIPTION:
BAUMANN CREEK 54.0
END DESCRIPTION:
XS GIS Cut Line= 3
      2754855.67     10291953.09      2754193.21     10291145.93
      2753855.68     10290803.11
#Sta/Elev= 30
  3955.8 1574.29  4090.7 1563.81  4105.0 1558.58  4168.9 1552.26  4183.2 1547.62
  4261.5 1535.36  4345.8 1527.46  4453.1 1522.51  4545.6 1520.61  4588.7 1521.53
  4674.2 1518.94  4751.6 1516.28  4794.6 1517.09  4836.3 1514.29  4928.8 1512.80
  4951.1 1511.48  4957.5 1509.20  4978.3 1506.86  4996.6 1506.25  4996.8 1505.75
  5000.6 1506.25  5078.0 1510.17  5085.1 1508.90  5134.6 1510.79  5162.9 1509.72
  5226.6 1514.41  5304.3 1523.40  5368.0 1536.58  5452.9 1547.09  5481.1 1548.68
#Mann=5,-1,0
  3955.8    0.12       0  4345.8    0.05       0  4674.2    0.12       0
  4996.6    0.07       0  5000.6    0.12       0
Bank Sta=4996.6,5000.6
Exp/Cntr=0.3,0.1

Type RM Length L Ch R = 1,26500,500,500,500
BEGIN DESCRIPTION:
BAUMANN CREEK 53.0
END DESCRIPTION:
XS GIS Cut Line= 3
      2754955.71     10291453.14      2754307.43     10290673.70
      2753955.68     10290753.11
#Sta/Elev= 30
  3986.2 1553.72  4050.7 1549.54  4149.6 1535.03  4170.5 1530.18  4244.9 1521.52
  4306.5 1516.24  4377.4 1512.19  4433.4 1510.40  4453.3 1511.32  4682.1 1505.81
  4745.9 1505.74  4760.2 1504.02  4887.8 1503.54  4930.8 1505.24  4959.4 1504.17
  4965.9 1500.81  4973.8 1502.04  4980.3 1498.15  4994.6 1498.87  4995.5 1495.96
  4995.7 1495.46  4999.5 1495.96  5032.5 1499.79  5124.8 1504.43  5217.1 1514.39
  5244.9 1520.30  5293.2 1524.77  5336.4 1535.46  5341.6 1534.57  5360.6 1538.97
#Mann=7,-1,0
  3986.2    0.12       0  4244.9    0.05       0  4306.5    0.12       0
  4377.4    0.05       0  4453.3    0.12       0  4995.5    0.07       0
  4999.5    0.12       0
Bank Sta=4995.5,4999.5
Exp/Cntr=0.3,0.1

Type RM Length L Ch R = 1,26000,500,500,500
BEGIN DESCRIPTION:
BAUMANN CREEK 52.0
END DESCRIPTION:
XS GIS Cut Line= 3
      2754955.68     10291253.09      2754620.58     10290310.06
      2753605.66     10289303.09
#Sta/Elev= 30
  3999.2 1533.57  4031.0 1529.85  4040.2 1526.66  4045.5 1526.95  4084.1 1519.04
  4147.8 1516.76  4215.9 1511.70  4338.1 1504.83  4415.8 1503.95  4666.8 1498.45
  4784.5 1499.02  4922.5 1497.27  4970.0 1493.62  4975.5 1491.25  4993.4 1488.71
  4993.7 1488.21  4997.8 1488.71  5022.5 1494.21  5057.9 1498.95  5414.0 1501.88
  5637.7 1506.26  5800.3 1507.14  5878.9 1512.08  5984.2 1520.41  6040.8 1526.88
  6069.0 1531.77  6231.7 1549.65  6295.3 1558.55  6380.2 1576.03  6429.7 1582.89
#Mann=7,-1,0
  3999.2    0.12       0  4215.9    0.05       0  4415.8    0.12       0
  4993.4    0.07       0  4997.8    0.12       0  5414.0    0.05       0
  5878.9    0.12       0
Bank Sta=4993.4,4997.8
Exp/Cntr=0.3,0.1

Type RM Length L Ch R = 1,25500,500,500,500
BEGIN DESCRIPTION:
BAUMANN CREEK 51.0
END DESCRIPTION:
XS GIS Cut Line= 3
      2755355.69     10290203.11      2754972.36     10289962.86
      2753955.69     10289253.11
#Sta/Elev= 30
  4547.6 1505.87  4624.8 1499.38  4880.5 1485.47  4889.9 1487.08  4974.8 1488.10
  4984.2 1487.57  4995.1 1481.62  5005.2 1482.81  5008.9 1481.12  5009.3 1480.62
  5013.6 1481.12  5020.0 1485.16  5026.1 1486.24  5142.1 1490.47  5335.8 1493.90
  5443.1 1493.15  5600.9 1497.70  5671.7 1497.27  5690.1 1497.51  5788.5 1501.49
  5837.4 1506.17  5937.6 1523.52  6032.6 1533.85  6146.1 1555.17  6175.8 1559.11
  6181.9 1562.25  6190.6 1561.19  6196.7 1564.68  6203.3 1562.23  6239.9 1566.44
#Mann=6,-1,0
  4547.6    0.05       0  4624.8    0.12       0  5008.9    0.07       0
  5013.6    0.12       0  5671.7    0.05       0  5690.1    0.12       0
Bank Sta=5008.9,5013.6
Exp/Cntr=0.3,0.1

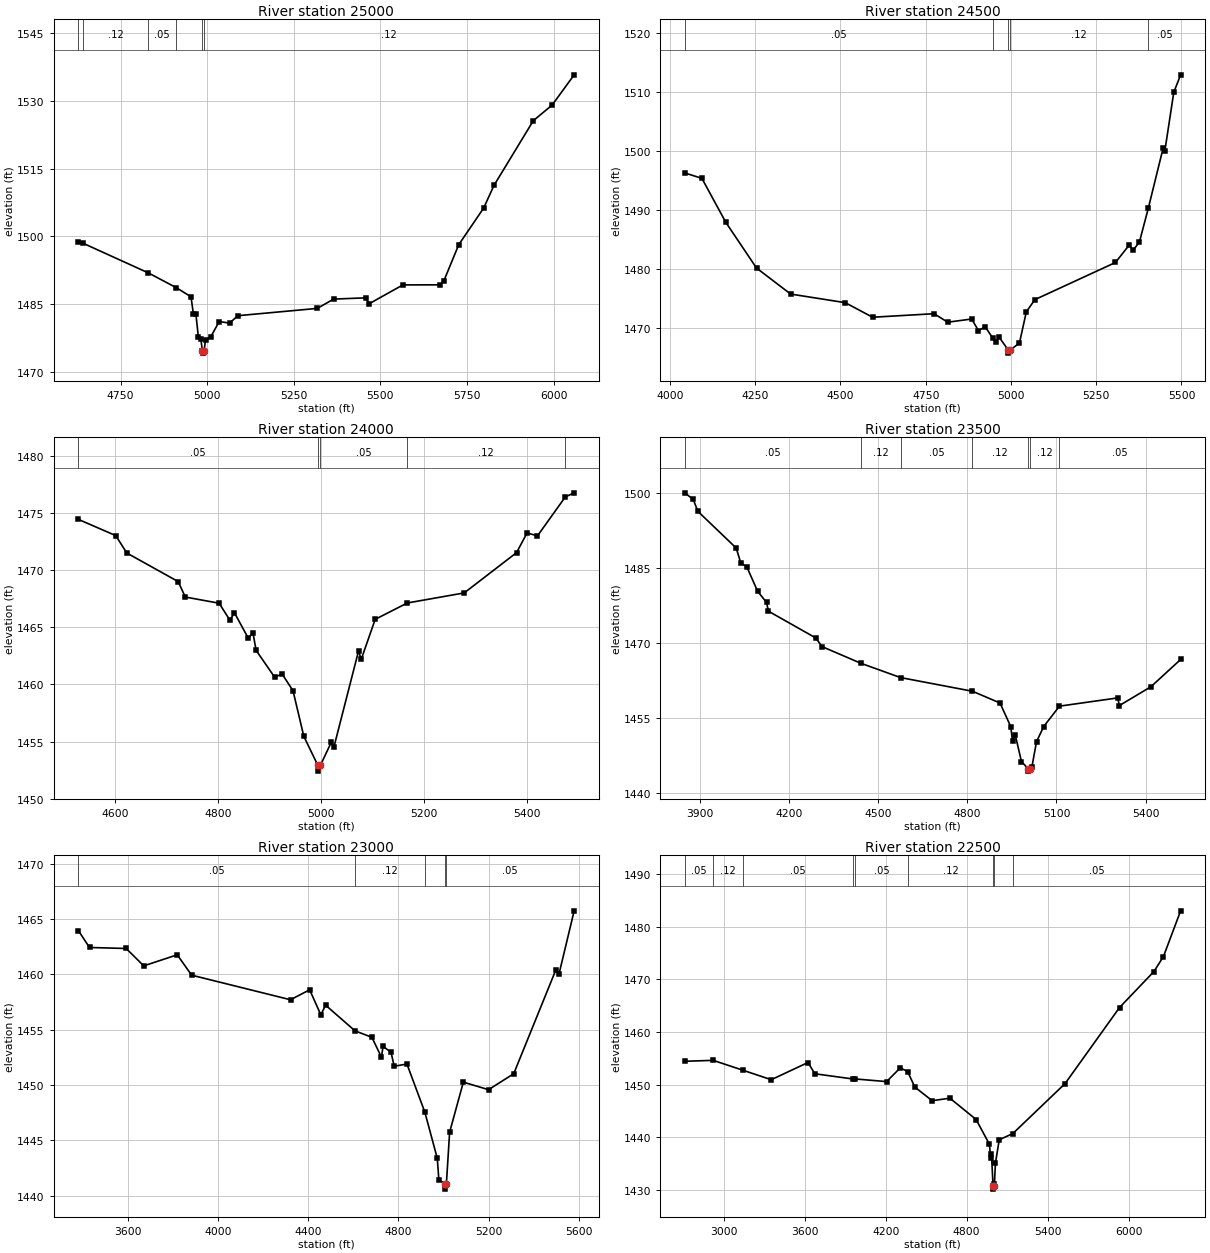
Type RM Length L Ch R = 1,25000,500,500,500
BEGIN DESCRIPTION:
BAUMANN CREEK 50.0
END DESCRIPTION:
XS GIS Cut Line= 3
      2755455.65     10289803.08      2755191.14     10289541.51
      2754205.71     10289153.12
#Sta/Elev= 30
  4628.0 1498.70  4642.6 1498.47  4829.8 1491.95  4910.4 1488.69  4953.2 1486.66
  4960.3 1482.76  4967.3 1482.86  4974.5 1477.71  4981.5 1477.35  4986.2 1474.68
  4986.6 1474.18  4990.9 1474.68  4995.3 1477.17  5010.3 1477.79  5034.6 1481.17
  5064.4 1480.83  5088.8 1482.47  5317.6 1484.08  5364.9 1486.14  5457.3 1486.42
  5467.8 1485.13  5564.8 1489.28  5672.3 1489.30  5683.0 1490.16  5726.0 1498.18
  5798.0 1506.30  5827.8 1511.31  5941.4 1525.65  5995.6 1529.09  6059.2 1535.79
#Mann=6,-1,0
  4628.0    0.05       0  4642.6    0.12       0  4829.8    0.05       0
  4910.4    0.12       0  4986.2    0.07       0  4990.9    0.12       0
Bank Sta=4986.2,4990.9
Exp/Cntr=0.3,0.1

Type RM Length L Ch R = 1,24500,500,500,500
BEGIN DESCRIPTION:
BAUMANN CREEK 49.0
END DESCRIPTION:
XS GIS Cut Line= 3
      2756055.71     10289103.11      2755100.40     10289055.52
      2754605.67     10289003.11
#Sta/Elev= 30
  4043.5 1496.32  4093.6 1495.41  4163.7 1487.96  4253.8 1480.21  4353.9 1475.80
  4514.1 1474.34  4594.2 1471.87  4774.4 1472.47  4814.5 1471.03  4884.6 1471.57
  4904.6 1469.62  4924.6 1470.24  4946.4 1468.35  4954.7 1467.64  4964.7 1468.54
  4992.3 1466.29  4992.7 1465.79  4997.1 1466.29  5024.9 1467.50  5045.0 1472.79
  5070.2 1474.86  5306.4 1481.15  5346.6 1484.09  5358.4 1483.23  5376.8 1484.64
  5403.2 1490.45  5446.1 1500.51  5451.1 1500.00  5477.4 1509.98  5497.5 1512.95
#Mann=5,-1,0
  4043.5    0.05       0  4946.4    0.12       0  4992.3    0.07       0
  4997.1    0.12       0  5403.2    0.05       0
Bank Sta=4992.3,4997.1
Exp/Cntr=0.3,0.1

Type RM Length L Ch R = 1,24000,500,500,500
BEGIN DESCRIPTION:
BAUMANN CREEK 48.0
END DESCRIPTION:
XS GIS Cut Line= 3
      2755655.66     10289053.08      2755389.17     10288664.35
      2754905.65     10288753.12
#Sta/Elev= 30
  4528.7 1474.43  4601.4 1473.01  4622.8 1471.49  4722.6 1468.99  4736.4 1467.64
  4802.1 1467.10  4823.1 1465.61  4831.8 1466.27  4859.0 1464.02  4867.8 1464.53
  4873.9 1462.98  4909.7 1460.65  4924.6 1460.90  4945.6 1459.45  4966.6 1455.46
  4993.9 1452.92  4994.3 1452.42  4998.8 1452.92  5019.8 1454.93  5024.9 1454.50
  5072.9 1462.93  5078.0 1462.18  5105.2 1465.69  5167.6 1467.12  5278.1 1468.00
  5379.7 1471.52  5400.1 1473.24  5420.4 1472.99  5474.4 1476.39  5491.6 1476.75
#Mann=5,-1,0
  4528.7    0.05       0  4993.9    0.05       0  4998.8    0.05       0
  5167.6    0.12       0  5474.4    0.05       0
Bank Sta=4993.9,4998.8
Exp/Cntr=0.3,0.1

Type RM Length L Ch R = 1,23500,500,500,500
BEGIN DESCRIPTION:
BAUMANN CREEK 47.0
END DESCRIPTION:
XS GIS Cut Line= 3
      2756155.70     10289153.14      2755522.49     10288190.53
      2755005.65     10288153.11
#Sta/Elev= 30
  3847.8 1500.09  3876.4 1498.76  3891.5 1496.41  4021.0 1489.05  4036.1 1486.12
  4057.2 1485.22  4093.3 1480.39  4123.1 1478.19  4129.5 1476.43  4289.2 1471.07
  4310.3 1469.34  4441.5 1466.00  4574.9 1463.15  4817.0 1460.42  4909.7 1458.07
  4945.9 1453.35  4951.9 1450.48  4961.0 1451.70  4982.0 1446.36  5004.3 1444.95
  5004.7 1444.45  5009.3 1444.95  5016.9 1445.21  5032.7 1450.33  5057.0 1453.37
  5110.1 1457.44  5306.5 1459.09  5311.6 1457.55  5417.9 1461.31  5518.2 1466.77
#Mann=7,-1,0
  3847.8    0.05       0  4441.5    0.12       0  4574.9    0.05       0
  4817.0    0.12       0  5004.3    0.07       0  5009.3    0.12       0
  5110.1    0.05       0
Bank Sta=5004.3,5009.3
Exp/Cntr=0.3,0.1

Type RM Length L Ch R = 1,23000,500,500,500
BEGIN DESCRIPTION:
BAUMANN CREEK 46.0
END DESCRIPTION:
XS GIS Cut Line= 3
      2756705.69     10288853.12      2755574.91     10287695.57
      2755055.67     10287953.12
#Sta/Elev= 30
  3381.8 1463.95  3431.3 1462.42  3593.9 1462.33  3671.8 1460.76  3820.2 1461.76
  3884.0 1459.92  4322.3 1457.70  4407.2 1458.60  4456.7 1456.34  4477.9 1457.21
  4608.3 1454.89  4682.9 1454.31  4725.3 1452.52  4732.5 1453.49  4767.8 1452.96
  4781.9 1451.70  4838.5 1451.89  4917.6 1447.56  4973.0 1443.37  4979.9 1441.41
  5008.3 1441.10  5008.7 1440.60  5013.3 1441.10  5027.6 1445.74  5088.4 1450.26
  5200.1 1449.58  5311.7 1451.02  5498.3 1460.39  5512.6 1460.04  5579.6 1465.73
#Mann=5,-1,0
  3381.8    0.05       0  4608.3    0.12       0  4917.6    0.05       0
  5008.3    0.05       0  5013.3    0.05       0
Bank Sta=5008.3,5013.3
Exp/Cntr=0.3,0.1

Type RM Length L Ch R = 1,22500,500,500,500
BEGIN DESCRIPTION:
BAUMANN CREEK 45.0
END DESCRIPTION:
XS GIS Cut Line= 3
      2757405.65     10288503.09      2755518.64     10287207.78
      2754505.72     10288153.08
#Sta/Elev= 30
  2711.2 1454.44  2921.2 1454.62  3139.6 1452.76  3352.0 1450.94  3624.0 1454.21
  3674.8 1452.07  3959.8 1451.07  3972.4 1451.09  4206.7 1450.58  4308.2 1453.20
  4363.0 1452.47  4415.8 1449.54  4544.4 1446.95  4675.7 1447.43  4869.9 1443.38
  4968.7 1438.67  4977.5 1436.10  4983.6 1436.84  4995.9 1430.65  4996.3 1430.15
  5001.0 1430.65  5005.7 1431.09  5013.0 1435.05  5041.3 1439.53  5142.1 1440.71
  5529.4 1450.21  5932.9 1464.66  6187.4 1471.49  6258.3 1474.35  6385.5 1483.03
#Mann=9,-1,0
  2711.2    0.05       0  2921.2    0.12       0  3139.6    0.05       0
  3959.8    0.12       0  3972.4    0.05       0  4363.0    0.12       0
  4995.9    0.07       0  5001.0    0.12       0  5142.1    0.05       0
Bank Sta=4995.9,5001
Exp/Cntr=0.3,0.1

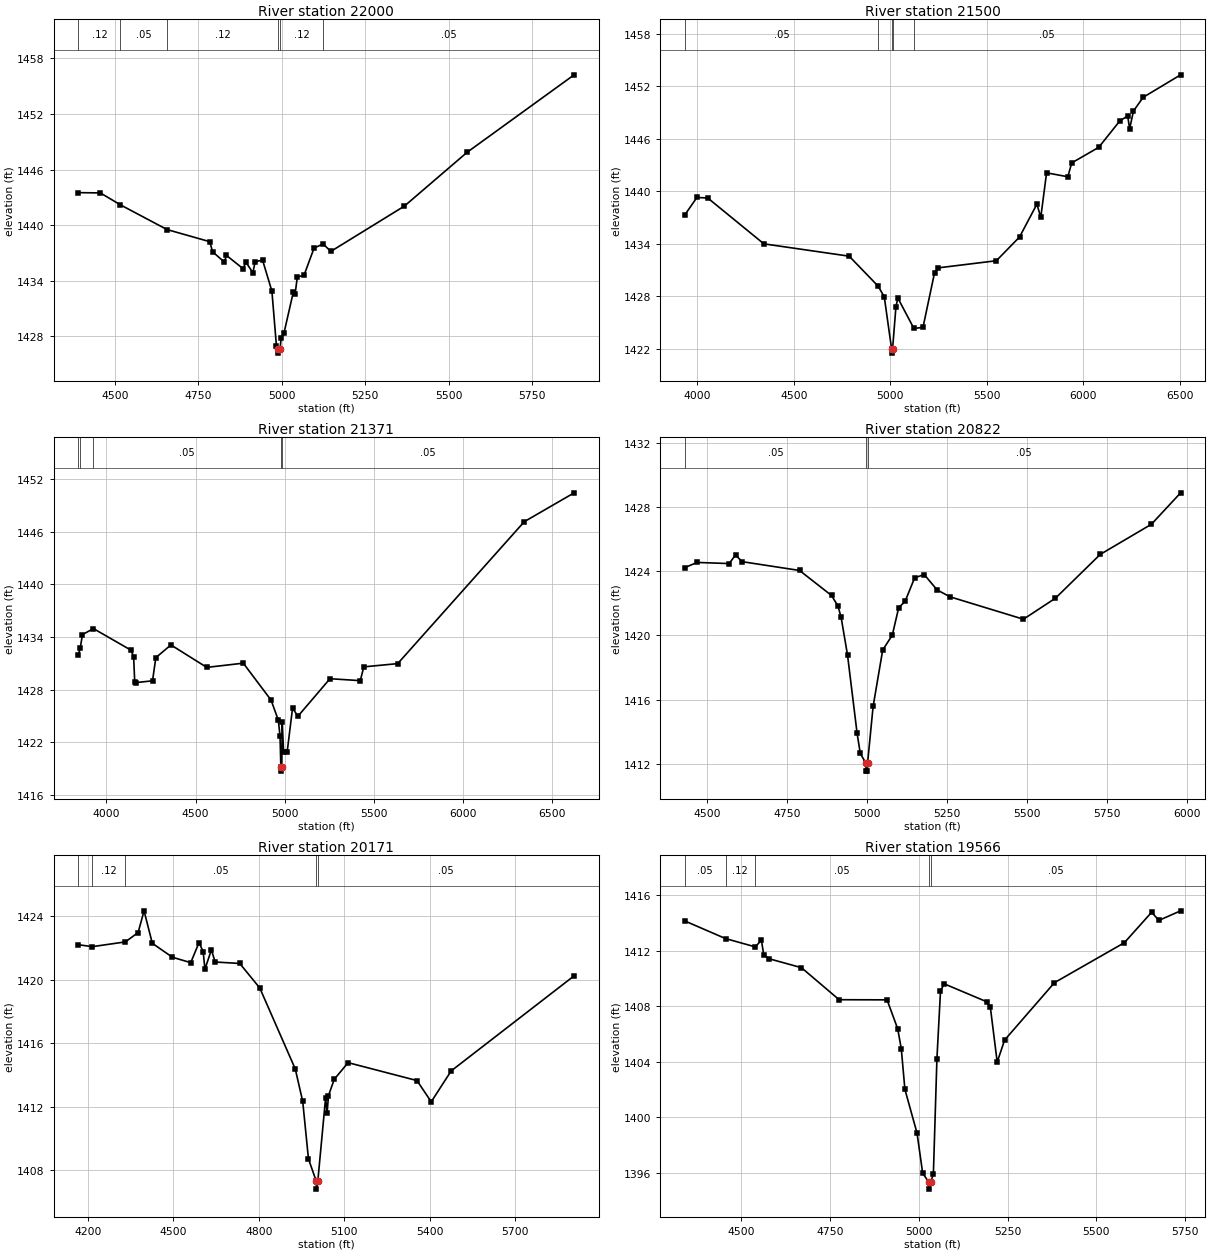
Type RM Length L Ch R = 1,22000,500,500,500
BEGIN DESCRIPTION:
BAUMANN CREEK 44.0
END DESCRIPTION:
XS GIS Cut Line= 3
      2755868.31     10287173.05      2755381.83     10286805.19
      2754508.73     10286872.63
#Sta/Elev= 30
  4390.1 1443.50  4456.1 1443.47  4516.3 1442.18  4656.0 1439.51  4784.0 1438.20
  4792.3 1437.11  4827.6 1436.00  4833.9 1436.72  4883.9 1435.28  4892.1 1435.99
  4913.0 1434.85  4919.9 1436.03  4942.1 1436.21  4970.1 1432.85  4983.7 1426.91
  4989.4 1426.66  4989.8 1426.16  4994.7 1426.66  4997.6 1427.75  5006.2 1428.32
  5034.6 1432.81  5039.6 1432.56  5046.3 1434.39  5066.3 1434.57  5096.4 1437.51
  5123.5 1437.96  5146.6 1437.15  5367.2 1442.05  5555.0 1447.86  5875.7 1456.23
#Mann=6,-1,0
  4390.1    0.12       0  4516.3    0.05       0  4656.0    0.12       0
  4989.4    0.07       0  4994.7    0.12       0  5123.5    0.05       0
Bank Sta=4989.4,4994.7
Exp/Cntr=0.3,0.1

Type RM Length L Ch R = 1,21500,129,129,129
BEGIN DESCRIPTION:
BAUMANN CREEK 43.0
END DESCRIPTION:
XS GIS Cut Line= 4
      2756622.34     10286775.04      2756316.53     10286492.93
      2755674.61     10286401.15      2754171.62     10286425.93
#Sta/Elev= 30
  3935.5 1437.29  3998.4 1439.29  4054.6 1439.22  4344.9 1433.99  4786.8 1432.58
  4937.1 1429.15  4968.6 1427.93  5006.3 1422.01  5006.7 1421.51  5011.6 1422.01
  5028.9 1426.81  5038.9 1427.80  5121.8 1424.33  5169.0 1424.45  5229.0 1430.71
  5249.0 1431.25  5549.0 1432.06  5669.0 1434.77  5759.0 1438.53  5779.0 1437.01
  5809.0 1442.10  5919.1 1441.65  5939.1 1443.23  6079.1 1445.01  6189.1 1448.05
  6229.1 1448.58  6239.1 1447.13  6259.1 1449.16  6309.1 1450.72  6503.2 1453.29
#Mann=5,-1,0
  3935.5    0.05       0  4937.1    0.12       0  5006.3    0.07       0
  5011.6    0.12       0  5121.8    0.05       0
Bank Sta=5006.3,5011.6
Exp/Cntr=0.3,0.1

Type RM Length L Ch R = 1,21371,549,549,549
BEGIN DESCRIPTION:
Mapping XS e7d93e86
END DESCRIPTION:
XS GIS Cut Line= 6
      2756803.91     10286558.62      2756454.77     10286293.27
      2756329.09     10286265.34      2756000.93     10286265.34
      2755700.70     10286293.27      2754115.70     10286272.32
#Sta/Elev= 30
  3842.1 1431.99  3852.5 1432.72  3865.4 1434.28  3926.9 1434.96  4137.7 1432.50
  4152.3 1431.76  4158.5 1428.87  4166.4 1428.81  4258.4 1429.01  4276.9 1431.65
  4361.6 1433.10  4562.8 1430.54  4767.7 1431.02  4923.6 1426.81  4963.8 1424.55
  4973.8 1422.77  4978.4 1419.22  4978.9 1418.72  4983.8 1419.22  4986.1 1424.36
  4993.9 1420.85  5014.0 1420.94  5044.1 1425.90  5074.1 1424.97  5254.1 1429.25
  5424.1 1429.03  5444.1 1430.60  5634.1 1430.97  6344.2 1447.14  6624.2 1450.43
#Mann=5,-1,0
  3842.1    0.05       0  3852.5    0.12       0  3926.9    0.05       0
  4978.4    0.03       0  4983.8    0.05       0
Bank Sta=4978.4,4983.8
Exp/Cntr=0.3,0.1

Type RM Length L Ch R = 1,20822,651,651,651
BEGIN DESCRIPTION:
Mapping XS a778618e
END DESCRIPTION:
XS GIS Cut Line= 2
      2756224.38     10285776.59      2754674.30     10285783.57
#Sta/Elev= 30
  4430.4 1424.23  4469.1 1424.55  4569.1 1424.48  4589.1 1425.02  4609.1 1424.60
  4789.1 1424.05  4889.1 1422.49  4909.1 1421.84  4919.1 1421.13  4939.1 1418.78
  4969.1 1413.89  4979.1 1412.64  4996.4 1412.04  4996.9 1411.54  5001.4 1411.54
  5001.8 1412.04  5019.1 1415.57  5049.1 1419.09  5079.1 1420.02  5099.1 1421.73
  5119.1 1422.12  5149.1 1423.60  5179.1 1423.79  5219.1 1422.84  5259.1 1422.41
  5489.1 1421.01  5589.1 1422.32  5729.1 1425.05  5889.1 1426.93  5980.5 1428.89
#Mann=3,-1,0
  4430.4    0.05       0  4996.4    0.03       0  5001.8    0.05       0
Bank Sta=4996.4,5001.8
Exp/Cntr=0.3,0.1

Type RM Length L Ch R = 1,20171,605,605,605
BEGIN DESCRIPTION:
Mapping XS b71f5193
END DESCRIPTION:
XS GIS Cut Line= 4
      2756224.39     10285518.28      2755784.48     10285176.13
      2755393.48     10285141.22      2754604.47     10285155.18
#Sta/Elev= 30
  4167.0 1422.21  4216.4 1422.09  4332.0 1422.39  4376.7 1422.98  4397.5 1424.35
  4426.5 1422.30  4497.1 1421.42  4561.3 1421.08  4590.3 1422.35  4604.7 1421.78
  4611.1 1420.67  4633.7 1421.89  4646.8 1421.12  4733.1 1421.03  4803.4 1419.48
  4927.9 1414.37  4954.0 1412.32  4974.1 1408.70  5001.5 1407.29  5001.9 1406.79
  5006.9 1407.29  5034.3 1412.56  5039.3 1411.58  5044.4 1412.69  5064.5 1413.72
  5113.2 1414.77  5354.7 1413.64  5404.7 1412.30  5474.7 1414.25  5906.0 1420.25
#Mann=5,-1,0
  4167.0    0.05       0  4216.4    0.12       0  4332.0    0.05       0
  5001.5    0.03       0  5006.9    0.05       0
Bank Sta=5001.5,5006.9
Exp/Cntr=0.3,0.1

Type RM Length L Ch R = 1,19566,566,566,566
BEGIN DESCRIPTION:
Mapping XS 84d47e47
END DESCRIPTION:
XS GIS Cut Line= 4
      2755868.30     10284924.80      2755575.02     10284596.61
      2754932.66     10284540.75      2754625.42     10284596.61
#Sta/Elev= 30
  4340.4 1414.16  4455.1 1412.89  4538.9 1412.29  4556.2 1412.77  4562.9 1411.72
  4577.1 1411.44  4669.1 1410.79  4775.3 1408.48  4910.4 1408.47  4940.5 1406.37
  4950.5 1404.93  4960.6 1402.02  4994.9 1398.85  5010.7 1395.97  5028.1 1395.32
  5028.5 1394.82  5033.5 1395.32  5040.9 1395.93  5050.9 1404.24  5060.9 1409.08
  5071.0 1409.63  5191.4 1408.33  5201.5 1407.92  5220.7 1403.98  5241.6 1405.57
  5382.1 1409.71  5579.0 1412.59  5656.0 1414.79  5676.3 1414.20  5737.6 1414.89
#Mann=5,-1,0
  4340.4    0.05       0  4455.1    0.12       0  4538.9    0.05       0
  5028.1    0.05       0  5033.5    0.05       0
Bank Sta=5028.1,5033.5
Exp/Cntr=0.3,0.1