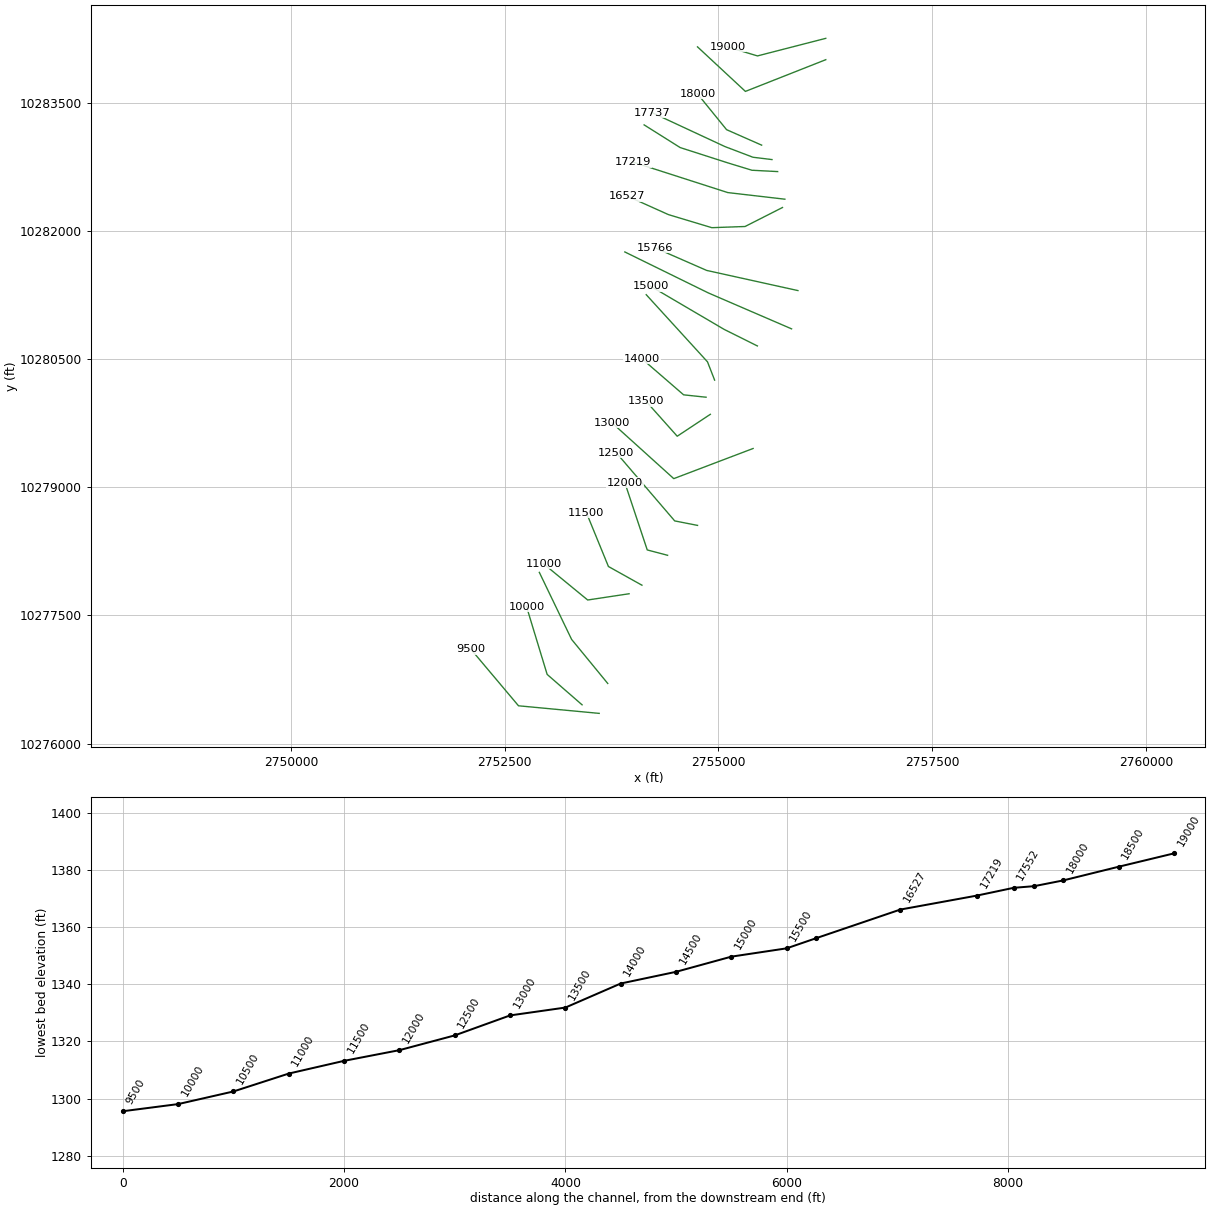
HEC-RAS study BAUMANN CREEK.prj: BAUMANN CREEK Base Level Engineering

--- BAUMANN CREEK.g01 (geometry) --- (continued)

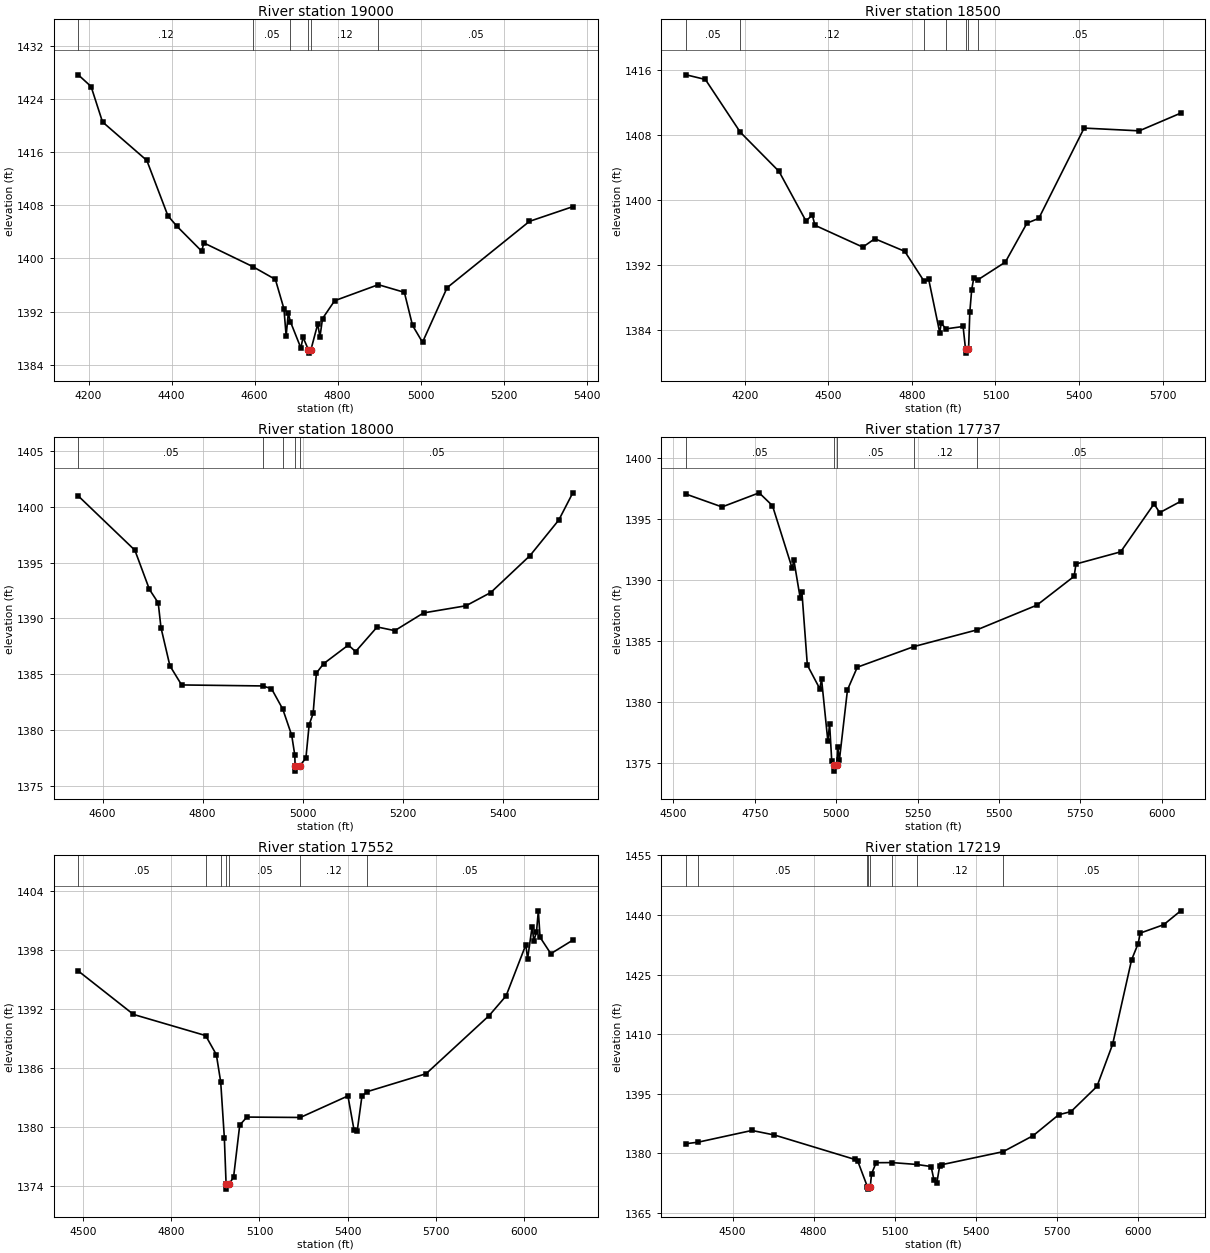
Type RM Length L Ch R = 1,19000,500,500,500
BEGIN DESCRIPTION:
BAUMANN CREEK 38.0
END DESCRIPTION:
XS GIS Cut Line= 3
      2756255.66     10284253.10      2755456.84     10284047.30
      2755105.64     10284153.13
#Sta/Elev= 30
  4175.1 1427.60  4206.0 1425.84  4233.5 1420.52  4340.3 1414.73  4391.1 1406.41
  4412.6 1404.85  4472.5 1401.09  4477.7 1402.33  4595.5 1398.77  4650.1 1396.84
  4670.7 1392.43  4676.0 1388.36  4681.2 1391.76  4686.3 1390.49  4711.5 1386.53
  4716.7 1388.14  4729.7 1386.26  4730.2 1385.76  4735.7 1386.26  4752.2 1390.15
  4757.4 1388.17  4763.7 1390.96  4792.9 1393.64  4898.1 1396.05  4960.9 1394.90
  4980.5 1389.94  5004.6 1387.39  5063.9 1395.60  5262.3 1405.57  5366.8 1407.78
#Mann=6,-1,0
  4175.1    0.12       0  4595.5    0.05       0  4686.3    0.12       0
  4729.7    0.05       0  4735.7    0.12       0  4898.1    0.05       0
Bank Sta=4729.7,4735.7
Exp/Cntr=0.3,0.1

Type RM Length L Ch R = 1,18500,500,500,500
BEGIN DESCRIPTION:
BAUMANN CREEK 37.0
END DESCRIPTION:
XS GIS Cut Line= 3
      2756255.67     10284003.11      2755315.76     10283632.07
      2754755.66     10284153.14
#Sta/Elev= 30
  3989.5 1415.37  4058.5 1414.80  4183.7 1408.31  4322.8 1403.48  4419.5 1397.38
  4442.6 1398.09  4451.8 1396.84  4623.8 1394.15  4666.8 1395.18  4774.3 1393.63
  4844.2 1389.92  4860.3 1390.18  4899.9 1383.62  4905.3 1384.76  4922.5 1384.08
  4983.8 1384.37  4992.5 1381.59  4993.0 1381.09  5002.3 1381.59  5003.5 1381.59
  5007.9 1386.14  5014.7 1388.92  5022.1 1390.33  5037.3 1390.13  5135.4 1392.30
  5213.1 1397.10  5255.6 1397.69  5418.3 1408.81  5616.2 1408.47  5765.0 1410.65
#Mann=7,-1,0
  3989.5    0.05       0  4183.7    0.12       0  4844.2    0.05       0
  4922.5    0.12       0  4992.5    0.07       0  5002.3    0.12       0
  5037.3    0.05       0
Bank Sta=4992.5,5002.3
Exp/Cntr=0.3,0.1

Type RM Length L Ch R = 1,18000,263,263,263
BEGIN DESCRIPTION:
BAUMANN CREEK 36.0
END DESCRIPTION:
XS GIS Cut Line= 3
      2755505.71     10283003.10      2755095.42     10283184.26
      2754755.69     10283603.10
#Sta/Elev= 30
  4551.5 1400.99  4664.6 1396.12  4693.6 1392.61  4711.2 1391.40  4716.7 1389.18
  4734.5 1385.76  4757.9 1384.04  4919.8 1383.95  4937.4 1383.71  4960.0 1381.87
  4977.9 1379.51  4984.0 1377.74  4984.6 1376.81  4985.1 1376.31  4994.5 1376.81
  5006.2 1377.49  5012.7 1380.48  5020.6 1381.48  5027.1 1385.10  5041.4 1385.94
  5091.0 1387.62  5105.4 1387.03  5148.5 1389.24  5183.7 1388.91  5241.2 1390.50
  5325.9 1391.14  5375.5 1392.33  5453.8 1395.64  5511.3 1398.83  5539.3 1401.27
#Mann=5,-1,0
  4551.5    0.05       0  4919.8    0.12       0  4960.0    0.05       0
  4984.6    0.05       0  4994.5    0.05       0
Bank Sta=4984.6,4994.5
Exp/Cntr=0.3,0.1

Type RM Length L Ch R = 1,17737,185,185,185
BEGIN DESCRIPTION:
Mapping XS fc74e2e7
END DESCRIPTION:
XS GIS Cut Line= 4
      2755626.46     10282834.24      2755403.96     10282861.57
      2755076.01     10282986.50      2754221.01     10283384.72
#Sta/Elev= 30
  4539.5 1397.06  4649.7 1396.01  4763.7 1397.17  4804.6 1396.11  4864.9 1390.98
  4870.3 1391.63  4889.6 1388.53  4895.0 1388.98  4911.6 1383.01  4949.8 1381.07
  4955.2 1381.86  4974.6 1376.76  4979.9 1378.19  4986.5 1375.12  4992.3 1374.80
  4992.8 1374.30  5002.2 1374.80  5004.7 1376.32  5010.0 1375.21  5034.8 1380.98
  5064.9 1382.84  5239.3 1384.54  5431.3 1385.90  5616.4 1387.94  5730.7 1390.31
  5736.2 1391.32  5873.5 1392.32  5976.0 1396.26  5993.4 1395.54  6057.8 1396.47
#Mann=5,-1,0
  4539.5    0.05       0  4992.3    0.05       0  5002.2    0.05       0
  5239.3    0.12       0  5431.3    0.05       0
Bank Sta=4992.3,5002.2
Exp/Cntr=0.3,0.1

Type RM Length L Ch R = 1,17552,333,333,333
BEGIN DESCRIPTION:
Mapping XS 6985ed8d
END DESCRIPTION:
XS GIS Cut Line= 5
      2755692.89     10282693.69      2755392.25     10282709.31
      2755111.15     10282795.20      2754552.85     10282974.79
      2754131.21     10283240.27
#Sta/Elev= 30
  4484.6 1395.91  4672.1 1391.49  4917.2 1389.34  4953.6 1387.40  4968.4 1384.62
  4980.7 1378.96  4986.7 1374.22  4987.2 1373.72  4996.6 1374.22  5012.1 1374.94
  5033.0 1380.23  5057.2 1381.05  5238.9 1381.01  5400.5 1383.20  5421.5 1379.69
  5432.0 1379.64  5448.0 1383.16  5464.3 1383.62  5666.0 1385.46  5880.0 1391.37
  5937.7 1393.38  6004.8 1398.58  6010.7 1397.14  6026.0 1400.39  6031.9 1399.00
  6040.8 1399.85  6047.2 1402.03  6053.1 1399.34  6089.6 1397.67  6164.3 1399.05
#Mann=7,-1,0
  4484.6    0.05       0  4917.2    0.12       0  4968.4    0.05       0
  4986.7    0.05       0  4996.6    0.05       0  5238.9    0.12       0
  5464.3    0.05       0
Bank Sta=4986.7,4996.6
Exp/Cntr=0.3,0.1

Type RM Length L Ch R = 1,17219,692,692,692
BEGIN DESCRIPTION:
BAUMANN CREEK 34.0
END DESCRIPTION:
XS GIS Cut Line= 3
      2755777.17     10282370.56      2755109.75     10282448.00
      2754005.66     10282803.12
#Sta/Elev= 30
  4328.1 1382.44  4372.5 1382.82  4571.7 1385.77  4655.3 1384.62  4953.8 1378.46
  4963.8 1378.03  4999.3 1371.63  5000.0 1371.50  5000.5 1371.00  5009.9 1371.50
  5014.8 1374.84  5031.8 1377.65  5090.7 1377.68  5182.4 1377.21  5235.4 1376.69
  5245.9 1373.32  5256.4 1372.52  5266.9 1376.75  5277.4 1377.19  5502.1 1380.43
  5613.5 1384.47  5708.1 1389.73  5753.4 1390.51  5849.7 1396.86  5907.7 1407.47
  5978.0 1428.74  6002.2 1432.80  6010.1 1435.46  6096.7 1437.56  6159.8 1441.06
#Mann=8,-1,0
  4328.1    0.12       0  4372.5    0.05       0  4999.3    0.12       0
  5000.0    0.07       0  5009.9    0.12       0  5090.7    0.05       0
  5182.4    0.12       0  5502.1    0.05       0
Bank Sta=5000,5009.9
Exp/Cntr=0.3,0.1

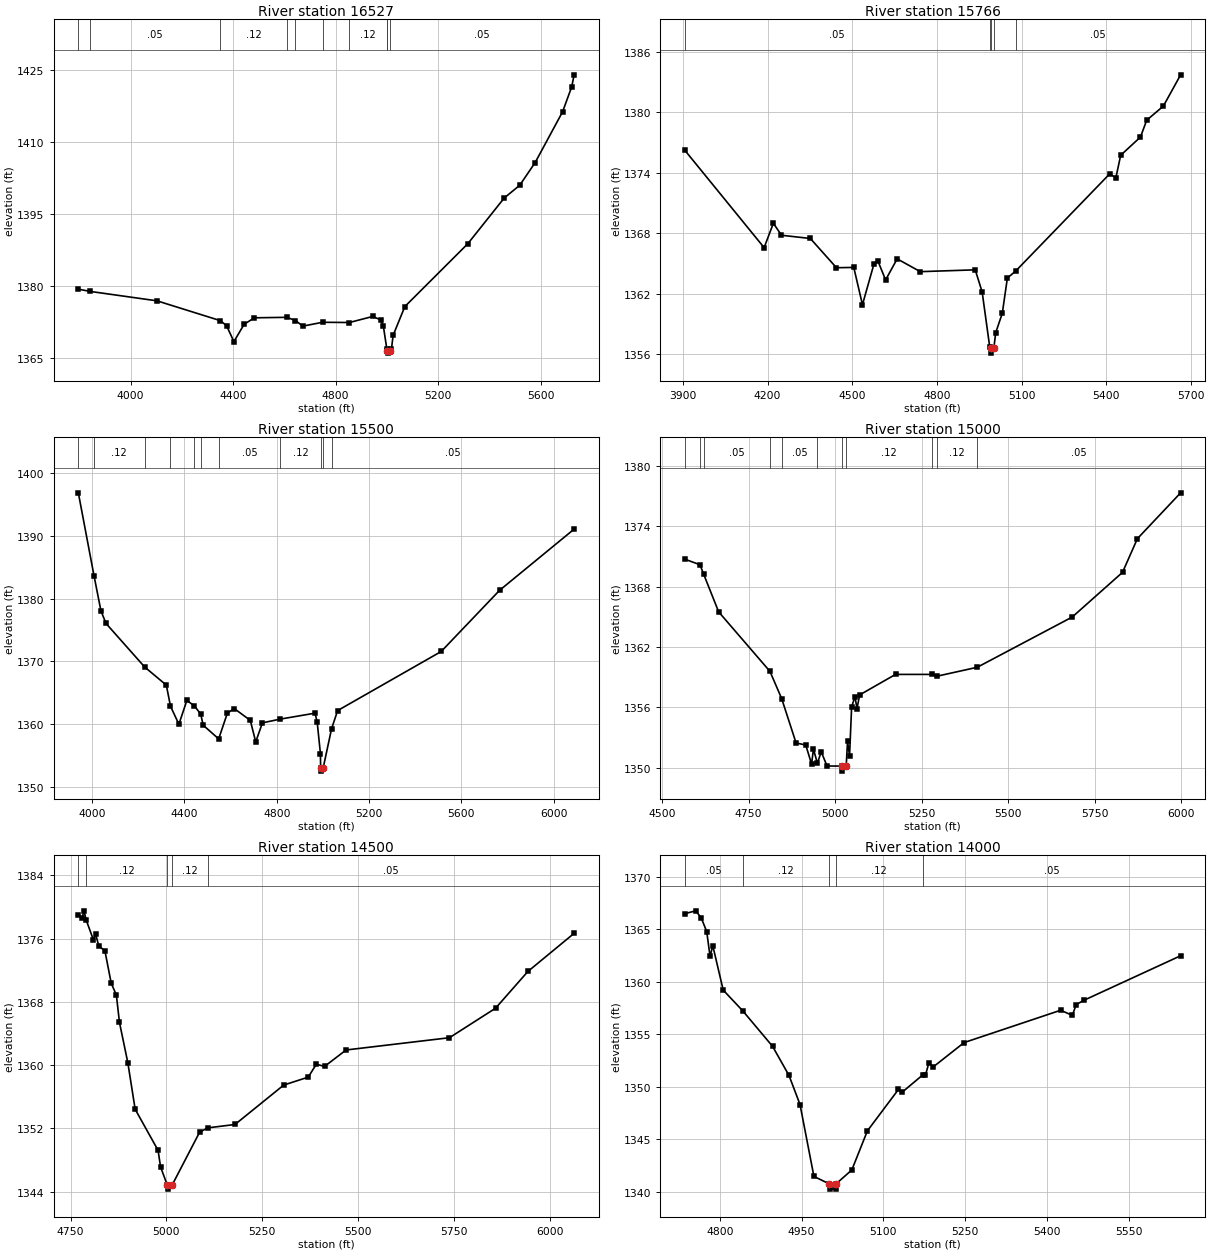
Type RM Length L Ch R = 1,16527,761,761,761
BEGIN DESCRIPTION:
Mapping XS bc5ef3b0
END DESCRIPTION:
XS GIS Cut Line= 5
      2755749.42     10282273.34      2755311.92     10282051.11
      2754923.04     10282037.22      2754416.09     10282190.00
      2753936.93     10282405.28
#Sta/Elev= 30
  3796.2 1379.42  3842.4 1378.95  4103.2 1376.99  4350.3 1372.87  4374.6 1371.82
  4403.2 1368.50  4443.2 1372.12  4483.3 1373.46  4609.9 1373.56  4643.4 1372.89
  4672.2 1371.73  4749.2 1372.53  4853.7 1372.48  4944.8 1373.74  4976.2 1373.02
  4986.2 1371.76  5000.0 1366.96  5002.0 1366.61  5002.5 1366.11  5013.0 1366.61
  5017.9 1366.93  5024.4 1369.81  5070.2 1375.80  5315.6 1388.86  5458.1 1398.40
  5518.3 1401.03  5578.7 1405.77  5685.9 1416.36  5721.2 1421.52  5730.8 1424.02
#Mann=10,-1,0
  3796.2    0.12       0  3842.4    0.05       0  4350.3    0.12       0
  4609.9    0.05       0  4643.4    0.12       0  4749.2    0.05       0
  4853.7    0.12       0  5000.0    0.05       0  5002.0    0.05       0
  5013.0    0.05       0
Bank Sta=5002,5013
Exp/Cntr=0.3,0.1

Type RM Length L Ch R = 1,15766,266,266,266
BEGIN DESCRIPTION:
BAUMANN CREEK 32.0
END DESCRIPTION:
XS GIS Cut Line= 3
      2755929.99     10281301.11      2754862.75     10281537.00
      2754255.71     10281803.10
#Sta/Elev= 30
  3907.0 1376.21  4187.9 1366.55  4220.6 1368.97  4249.4 1367.78  4351.6 1367.46
  4444.0 1364.56  4505.4 1364.59  4536.1 1360.89  4577.1 1364.96  4590.3 1365.26
  4618.1 1363.35  4659.0 1365.44  4741.0 1364.17  4935.5 1364.35  4960.0 1362.15
  4986.6 1356.74  4990.4 1356.59  4990.9 1356.09  5001.4 1356.59  5008.0 1358.12
  5031.3 1360.04  5049.3 1363.54  5078.4 1364.22  5411.7 1373.87  5433.5 1373.48
  5450.5 1375.71  5520.6 1377.52  5542.7 1379.19  5601.7 1380.59  5662.8 1383.69
#Mann=5,-1,0
  3907.0    0.05       0  4986.6    0.12       0  4990.4    0.07       0
  5001.4    0.12       0  5078.4    0.05       0
Bank Sta=4990.4,5001.4
Exp/Cntr=0.3,0.1

Type RM Length L Ch R = 1,15500,500,500,500
BEGIN DESCRIPTION:
BAUMANN CREEK 31.0
END DESCRIPTION:
XS GIS Cut Line= 3
      2755855.69     10280853.11      2754883.03     10281273.19
      2753905.70     10281753.10
#Sta/Elev= 30
  3940.5 1396.82  4008.4 1383.64  4038.5 1378.04  4060.3 1376.05  4227.7 1369.12
  4321.8 1366.23  4339.8 1362.87  4376.2 1360.01  4410.7 1363.79  4443.2 1362.94
  4471.1 1361.61  4481.2 1359.86  4548.6 1357.68  4586.1 1361.76  4615.9 1362.51
  4685.6 1360.62  4709.1 1357.20  4738.1 1360.23  4816.2 1360.83  4965.9 1361.77
  4975.3 1360.38  4989.4 1355.35  4990.3 1353.05  4990.8 1352.55  5001.3 1353.05
  5037.6 1359.27  5063.9 1362.18  5512.7 1371.58  5765.7 1381.31  6088.8 1391.05
#Mann=11,-1,0
  3940.5    0.05       0  4008.4    0.12       0  4227.7    0.05       0
  4339.8    0.12       0  4443.2    0.05       0  4471.1    0.12       0
  4548.6    0.05       0  4816.2    0.12       0  4990.3    0.07       0
  5001.3    0.12       0  5037.6    0.05       0
Bank Sta=4990.3,5001.3
Exp/Cntr=0.3,0.1

Type RM Length L Ch R = 1,15000,500,500,500
BEGIN DESCRIPTION:
BAUMANN CREEK 30.0
END DESCRIPTION:
XS GIS Cut Line= 3
      2755455.72     10280653.09      2755066.92     10280847.07
      2754205.69     10281353.11
#Sta/Elev= 30
  4565.5 1370.72  4609.3 1370.17  4619.9 1369.24  4663.4 1365.48  4811.7 1359.56
  4845.6 1356.85  4887.2 1352.44  4915.2 1352.24  4931.9 1350.35  4937.5 1351.83
  4948.8 1350.42  4959.9 1351.56  4976.7 1350.15  5020.1 1350.14  5020.6 1349.64
  5032.1 1350.14  5036.0 1352.61  5041.8 1351.17  5047.8 1356.04  5057.5 1357.04
  5063.3 1355.86  5071.0 1357.22  5174.7 1359.26  5280.9 1359.26  5294.5 1359.08
  5411.0 1359.97  5685.7 1364.97  5830.9 1369.41  5873.9 1372.76  5998.9 1377.32
#Mann=11,-1,0
  4565.5    0.05       0  4609.3    0.12       0  4619.9    0.05       0
  4811.7    0.12       0  4845.6    0.05       0  4948.8    0.12       0
  5020.1    0.07       0  5032.1    0.12       0  5280.9    0.05       0
  5294.5    0.12       0  5411.0    0.05       0
Bank Sta=5020.1,5032.1
Exp/Cntr=0.3,0.1

Type RM Length L Ch R = 1,14500,500,500,500
BEGIN DESCRIPTION:
BAUMANN CREEK 29.0
END DESCRIPTION:
XS GIS Cut Line= 3
      2754955.68     10280253.13      2754872.39     10280467.10
      2754155.70     10281253.10
#Sta/Elev= 30
  4770.4 1379.00  4780.0 1378.56  4785.3 1379.51  4790.6 1378.38  4809.8 1375.84
  4815.2 1376.60  4824.0 1375.04  4839.7 1374.46  4856.2 1370.35  4869.6 1368.87
  4877.7 1365.40  4899.5 1360.31  4918.6 1354.43  4978.4 1349.23  4985.0 1347.12
  5002.5 1344.83  5003.0 1344.33  5014.9 1344.83  5087.1 1351.56  5109.1 1352.08
  5179.0 1352.50  5306.0 1357.48  5370.2 1358.49  5391.1 1360.12  5412.7 1359.84
  5468.8 1361.92  5738.4 1363.47  5858.7 1367.20  5943.1 1371.85  6063.7 1376.67
#Mann=5,-1,0
  4770.4    0.05       0  4790.6    0.12       0  5002.5    0.07       0
  5014.9    0.12       0  5109.1    0.05       0
Bank Sta=5002.5,5014.9
Exp/Cntr=0.3,0.1

Type RM Length L Ch R = 1,14000,500,500,500
BEGIN DESCRIPTION:
BAUMANN CREEK 28.0
END DESCRIPTION:
XS GIS Cut Line= 3
      2754855.67     10280053.11      2754593.04     10280080.96
      2754105.66     10280503.13
#Sta/Elev= 30
  4735.9 1366.48  4756.0 1366.75  4766.0 1366.08  4776.1 1364.77  4782.2 1362.41
  4787.2 1363.43  4806.3 1359.20  4842.7 1357.19  4896.8 1353.84  4926.9 1351.07
  4947.1 1348.30  4972.6 1341.45  5000.8 1340.74  5001.3 1340.24  5012.7 1340.24
  5013.2 1340.74  5042.1 1342.07  5070.6 1345.79  5127.6 1349.74  5134.3 1349.47
  5171.9 1351.11  5177.0 1351.10  5183.6 1352.30  5191.3 1351.88  5247.9 1354.20
  5424.9 1357.28  5446.3 1356.79  5453.4 1357.82  5467.6 1358.23  5644.8 1362.47
#Mann=5,-1,0
  4735.9    0.05       0  4842.7    0.12       0  5000.8    0.07       0
  5013.2    0.12       0  5171.9    0.05       0
Bank Sta=5000.8,5013.2
Exp/Cntr=0.3,0.1

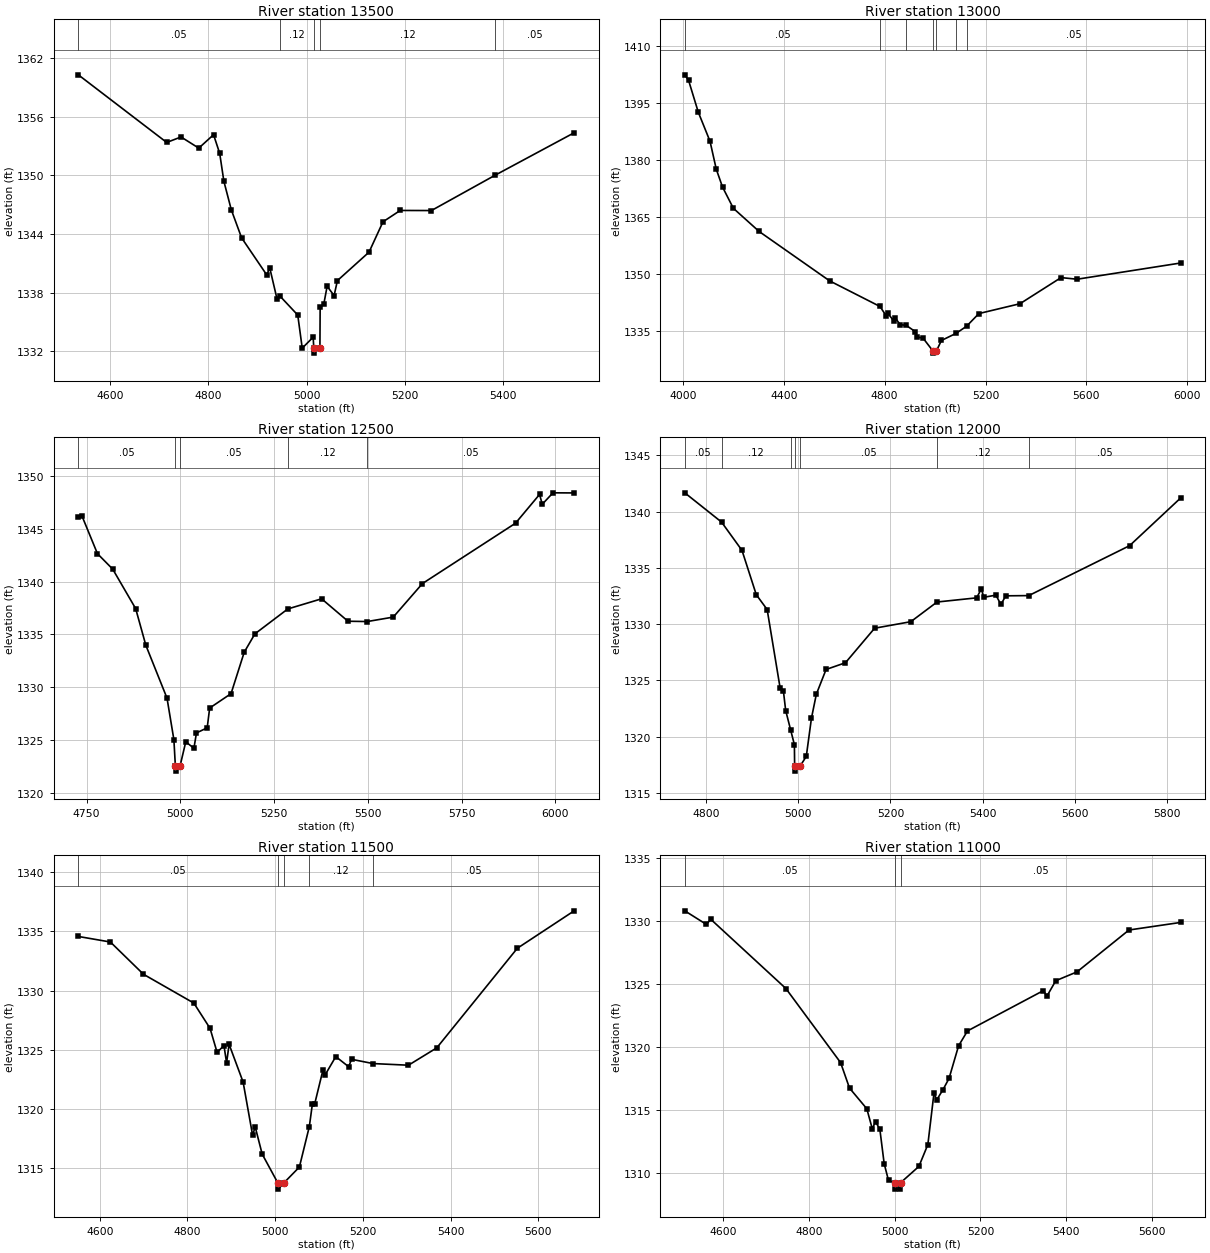
Type RM Length L Ch R = 1,13500,500,500,500
BEGIN DESCRIPTION:
BAUMANN CREEK 27.0
END DESCRIPTION:
XS GIS Cut Line= 3
      2754905.67     10279853.11      2754518.32     10279596.58
      2754155.66     10280003.14
#Sta/Elev= 30
  4535.4 1360.27  4715.3 1353.36  4744.5 1353.92  4780.6 1352.78  4810.7 1354.15
  4823.2 1352.24  4831.7 1349.39  4846.8 1346.48  4867.8 1343.61  4919.0 1339.82
  4925.0 1340.56  4940.0 1337.34  4945.5 1337.68  4982.1 1335.72  4991.2 1332.34
  5013.5 1333.46  5014.7 1332.33  5015.2 1331.83  5027.2 1332.33  5027.7 1336.52
  5035.2 1336.86  5041.9 1338.66  5056.1 1337.71  5062.8 1339.24  5127.2 1342.15
  5155.6 1345.25  5190.7 1346.41  5254.2 1346.40  5383.5 1350.00  5544.8 1354.35
#Mann=5,-1,0
  4535.4    0.05       0  4945.5    0.12       0  5014.7    0.07       0
  5027.2    0.12       0  5383.5    0.05       0
Bank Sta=5014.7,5027.2
Exp/Cntr=0.3,0.1

Type RM Length L Ch R = 1,13000,500,500,500
BEGIN DESCRIPTION:
BAUMANN CREEK 26.0
END DESCRIPTION:
XS GIS Cut Line= 3
      2755405.64     10279453.10      2754477.87     10279100.28
      2753755.70     10279753.10
#Sta/Elev= 30
  4007.4 1402.36  4022.4 1400.90  4060.8 1392.54  4107.4 1384.86  4132.2 1377.51
  4156.9 1372.83  4199.9 1367.22  4302.2 1361.11  4581.9 1348.10  4781.5 1341.36
  4806.8 1338.81  4812.1 1339.58  4836.9 1337.50  4842.2 1338.30  4861.7 1336.58
  4885.4 1336.39  4921.9 1334.71  4927.4 1333.32  4952.0 1333.04  4992.2 1329.58
  4992.7 1329.08  5004.7 1329.58  5024.9 1332.41  5083.0 1334.28  5124.5 1336.15
  5173.6 1339.50  5336.5 1342.09  5499.4 1348.97  5562.9 1348.54  5973.5 1352.81
#Mann=7,-1,0
  4007.4    0.05       0  4781.5    0.12       0  4885.4    0.05       0
  4992.2    0.05       0  5004.7    0.05       0  5083.0    0.12       0
  5124.5    0.05       0
Bank Sta=4992.2,5004.7
Exp/Cntr=0.3,0.1

Type RM Length L Ch R = 1,12500,500,500,500
BEGIN DESCRIPTION:
BAUMANN CREEK 25.0
END DESCRIPTION:
XS GIS Cut Line= 3
      2754755.70     10278553.11      2754489.00     10278605.50
      2753805.68     10279403.12
#Sta/Elev= 30
  4728.2 1346.07  4738.4 1346.15  4779.2 1342.63  4819.9 1341.17  4881.1 1337.44
  4908.2 1333.98  4964.7 1328.98  4983.0 1325.06  4986.9 1322.59  4987.4 1322.09
  4999.5 1322.59  5014.7 1324.86  5036.4 1324.25  5043.2 1325.70  5071.8 1326.18
  5078.4 1328.05  5135.4 1329.41  5170.6 1333.33  5199.1 1335.06  5286.7 1337.41
  5376.9 1338.37  5447.2 1336.25  5498.4 1336.22  5567.9 1336.64  5645.8 1339.81
  5893.9 1345.51  5958.1 1348.23  5965.2 1347.30  5993.8 1348.38  6050.3 1348.37
#Mann=5,-1,0
  4728.2    0.05       0  4986.9    0.05       0  4999.5    0.05       0
  5286.7    0.12       0  5498.4    0.05       0
Bank Sta=4986.9,4999.5
Exp/Cntr=0.3,0.1

Type RM Length L Ch R = 1,12000,500,500,500
BEGIN DESCRIPTION:
BAUMANN CREEK 24.0
END DESCRIPTION:
XS GIS Cut Line= 3
      2754405.66     10278203.12      2754167.61     10278265.93
      2753905.69     10279053.10
#Sta/Elev= 30
  4753.8 1341.68  4833.5 1339.08  4877.9 1336.56  4908.9 1332.62  4932.5 1331.30
  4960.6 1324.33  4967.6 1324.10  4972.7 1322.32  4983.6 1320.57  4991.6 1319.28
  4992.1 1317.43  4992.6 1316.93  5004.8 1317.43  5017.4 1318.24  5028.6 1321.64
  5039.2 1323.77  5060.3 1325.97  5102.4 1326.57  5165.7 1329.64  5244.2 1330.22
  5301.1 1331.97  5387.0 1332.34  5397.1 1333.13  5402.4 1332.39  5428.8 1332.58
  5439.7 1331.75  5450.2 1332.52  5500.1 1332.54  5718.9 1336.98  5829.6 1341.22
#Mann=7,-1,0
  4753.8    0.05       0  4833.5    0.12       0  4983.6    0.05       0
  4992.1    0.05       0  5004.8    0.05       0  5301.1    0.12       0
  5500.1    0.05       0
Bank Sta=4992.1,5004.8
Exp/Cntr=0.3,0.1

Type RM Length L Ch R = 1,11500,500,500,500
BEGIN DESCRIPTION:
BAUMANN CREEK 23.0
END DESCRIPTION:
XS GIS Cut Line= 3
      2754105.65     10277853.13      2753713.73     10278072.00
      2753455.69     10278703.09
#Sta/Elev= 30
  4551.1 1334.58  4624.2 1334.11  4699.6 1331.38  4814.5 1328.94  4851.5 1326.80
  4867.5 1324.77  4883.2 1325.34  4889.2 1323.88  4894.9 1325.45  4926.9 1322.25
  4948.6 1317.73  4954.3 1318.48  4970.3 1316.16  5006.4 1313.69  5006.9 1313.19
  5019.1 1313.69  5055.2 1315.06  5077.9 1318.49  5084.8 1320.39  5090.2 1320.42
  5108.8 1323.25  5114.2 1322.88  5138.2 1324.41  5167.6 1323.55  5174.1 1324.18
  5223.2 1323.82  5303.9 1323.68  5368.5 1325.15  5552.2 1333.58  5681.8 1336.75
#Mann=5,-1,0
  4551.1    0.05       0  5006.4    0.05       0  5019.1    0.05       0
  5077.9    0.12       0  5223.2    0.05       0
Bank Sta=5006.4,5019.1
Exp/Cntr=0.3,0.1

Type RM Length L Ch R = 1,11000,500,500,500
BEGIN DESCRIPTION:
BAUMANN CREEK 22.0
END DESCRIPTION:
XS GIS Cut Line= 3
      2753955.64     10277753.11      2753471.24     10277679.90
      2752955.69     10278103.10
#Sta/Elev= 30
  4510.1 1330.80  4560.6 1329.72  4570.7 1330.13  4746.0 1324.64  4873.6 1318.77
  4894.4 1316.75  4934.8 1315.11  4947.5 1313.53  4955.1 1314.08  4965.2 1313.49
  4975.3 1310.76  4985.4 1309.43  5000.2 1309.24  5000.7 1308.74  5012.9 1308.74
  5013.4 1309.24  5056.3 1310.54  5077.2 1312.27  5091.5 1316.35  5098.0 1315.82
  5112.3 1316.61  5126.7 1317.52  5148.9 1320.10  5169.7 1321.28  5347.0 1324.48
  5354.9 1324.03  5375.7 1325.26  5425.2 1325.96  5546.5 1329.28  5667.0 1329.88
#Mann=3,-1,0
  4510.1    0.05       0  5000.2    0.03       0  5013.4    0.05       0
Bank Sta=5000.2,5013.4
Exp/Cntr=0.3,0.1

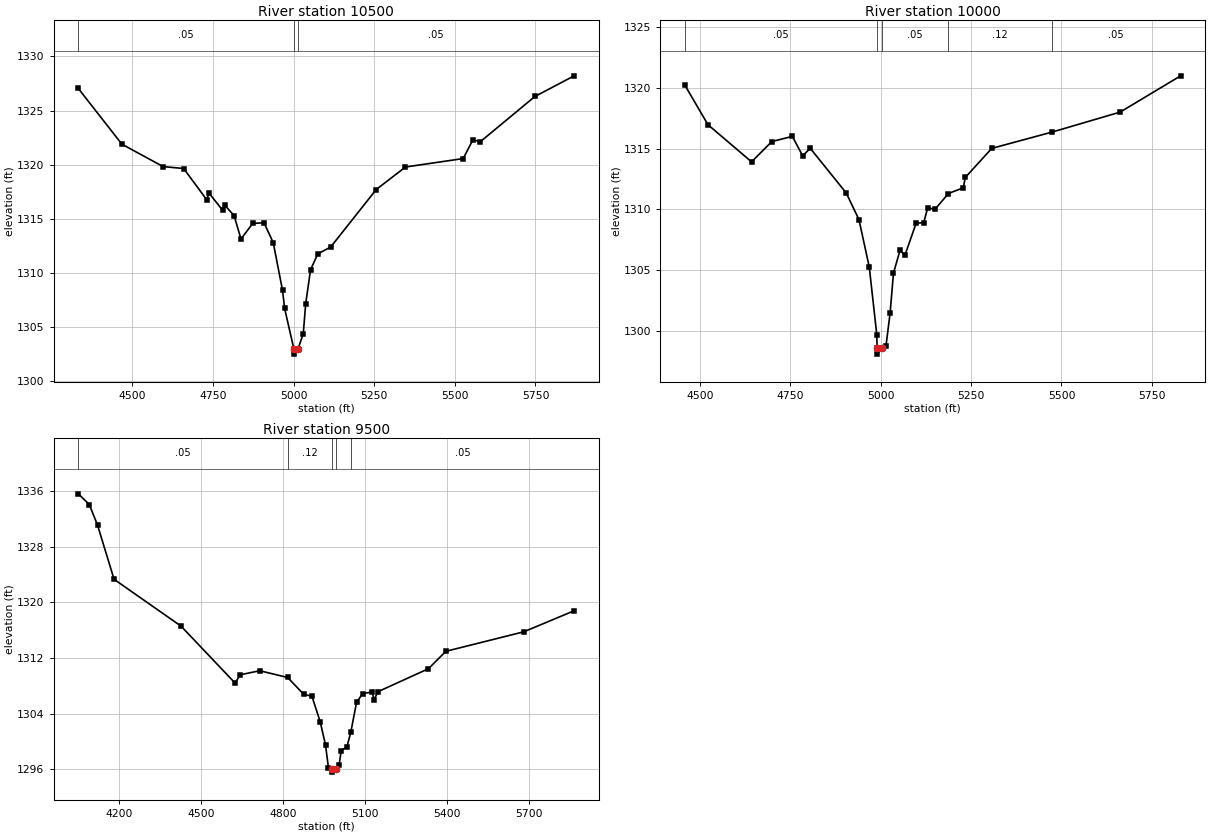
Type RM Length L Ch R = 1,10500,500,500,500
BEGIN DESCRIPTION:
BAUMANN CREEK 21.0
END DESCRIPTION:
XS GIS Cut Line= 3
      2753705.70     10276703.10      2753282.84     10277219.19
      2752905.70     10278003.08
#Sta/Elev= 30
  4332.8 1327.04  4467.8 1321.89  4595.5 1319.82  4659.4 1319.64  4731.1 1316.74
  4737.6 1317.38  4780.7 1315.76  4787.1 1316.24  4815.8 1315.28  4837.0 1313.12
  4873.3 1314.56  4908.4 1314.63  4937.1 1312.78  4965.8 1308.38  4972.3 1306.71
  5000.8 1302.98  5001.3 1302.48  5014.1 1302.98  5030.1 1304.37  5037.6 1307.13
  5052.7 1310.29  5075.3 1311.75  5115.0 1312.38  5256.4 1317.70  5346.9 1319.78
  5525.9 1320.56  5556.1 1322.30  5578.7 1322.11  5748.2 1326.30  5869.9 1328.21
#Mann=3,-1,0
  4332.8    0.05       0  5000.8    0.05       0  5014.1    0.05       0
Bank Sta=5000.8,5014.1
Exp/Cntr=0.3,0.1

Type RM Length L Ch R = 1,10000,500,500,500
BEGIN DESCRIPTION:
BAUMANN CREEK 20.0
END DESCRIPTION:
XS GIS Cut Line= 3
      2753405.68     10276453.11      2752997.03     10276809.31
      2752755.68     10277603.13
#Sta/Elev= 30
  4457.9 1320.24  4522.0 1316.97  4642.6 1313.91  4698.6 1315.58  4755.5 1316.01
  4784.0 1314.40  4804.9 1315.03  4904.6 1311.34  4939.7 1309.15  4968.2 1305.25
  4989.1 1299.66  4990.0 1298.56  4990.5 1298.06  5003.4 1298.56  5014.4 1298.71
  5026.0 1301.47  5035.3 1304.75  5053.6 1306.64  5066.7 1306.19  5098.0 1308.86
  5118.9 1308.89  5129.8 1310.12  5150.3 1310.00  5187.2 1311.30  5228.4 1311.77
  5233.9 1312.62  5307.1 1315.02  5473.7 1316.36  5662.4 1318.01  5829.7 1321.00
#Mann=5,-1,0
  4457.9    0.05       0  4990.0    0.05       0  5003.4    0.05       0
  5187.2    0.12       0  5473.7    0.05       0
Bank Sta=4990,5003.4
Exp/Cntr=0.3,0.1

Type RM Length L Ch R = 1,9500,500,500,500
BEGIN DESCRIPTION:
BAUMANN CREEK 19.0
END DESCRIPTION:
XS GIS Cut Line= 3
      2753605.66     10276353.11      2752662.13     10276441.87
      2752105.70     10277103.10
#Sta/Elev= 30
  4052.3 1335.64  4092.5 1334.09  4122.6 1331.12  4182.9 1323.33  4427.5 1316.59
  4624.8 1308.40  4644.9 1309.59  4715.2 1310.16  4817.2 1309.19  4875.9 1306.77
  4906.0 1306.49  4936.2 1302.80  4955.6 1299.47  4966.3 1296.19  4979.6 1296.06
  4980.1 1295.56  4993.1 1296.06  5005.2 1296.59  5013.0 1298.66  5033.8 1299.21
  5048.0 1301.31  5068.9 1305.59  5091.0 1306.86  5126.1 1307.11  5132.7 1305.95
  5147.0 1307.14  5331.6 1310.45  5395.4 1312.96  5680.2 1315.77  5864.2 1318.80
#Mann=5,-1,0
  4052.3    0.05       0  4817.2    0.12       0  4979.6    0.07       0
  4993.1    0.12       0  5048.0    0.05       0
Bank Sta=4979.6,4993.1
Exp/Cntr=0.3,0.1