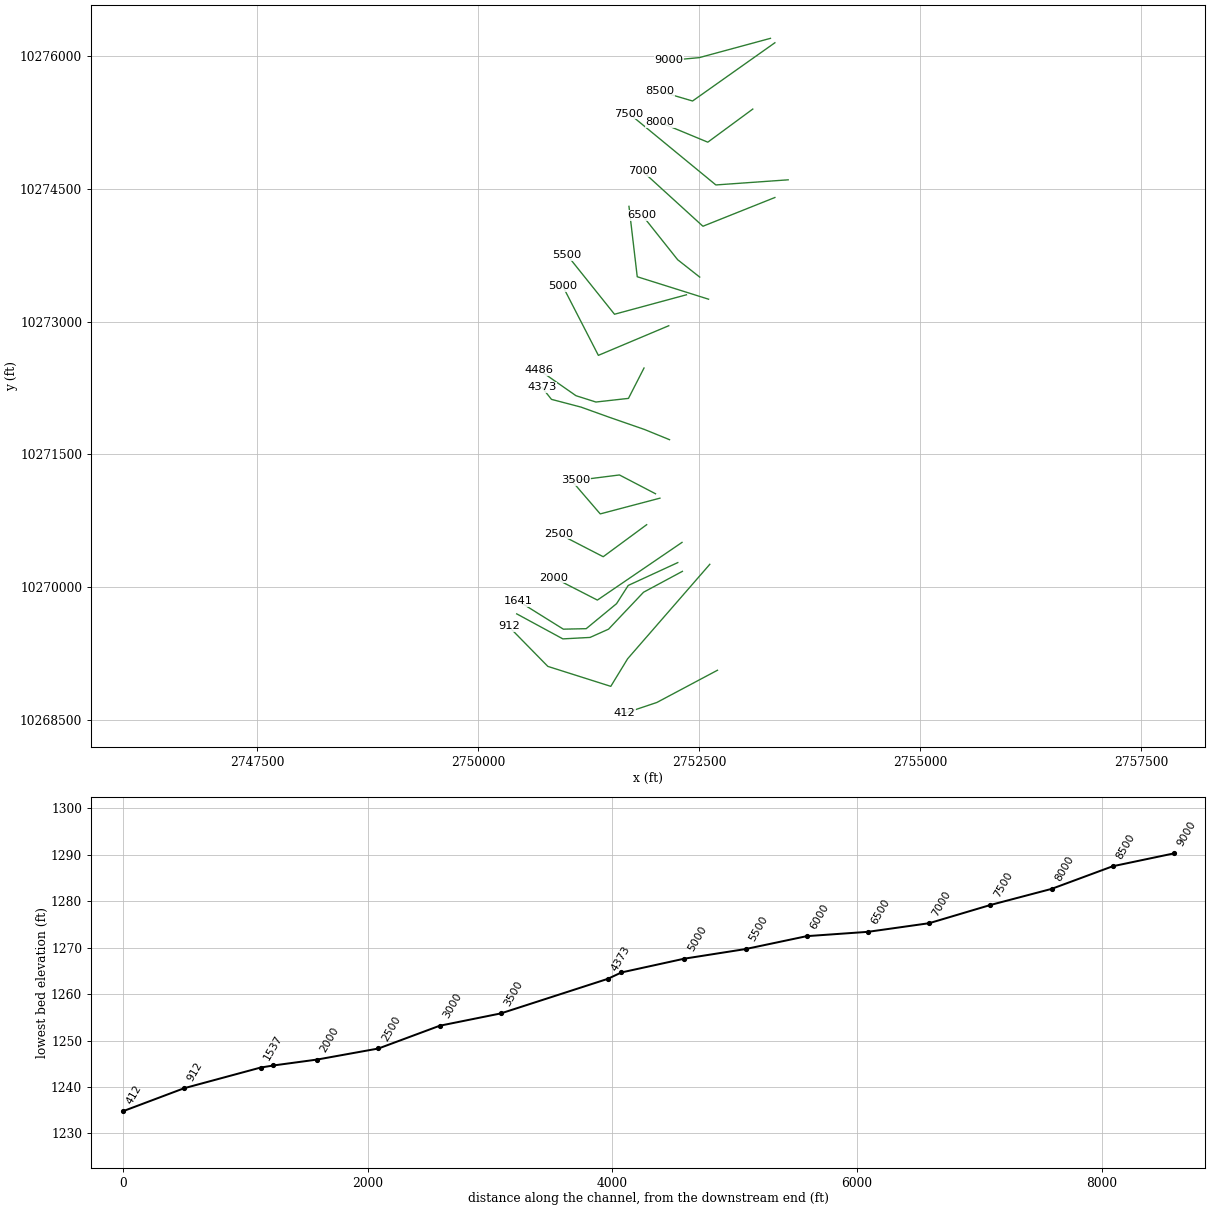
HEC-RAS study BAUMANN CREEK.prj: BAUMANN CREEK Base Level Engineering

--- BAUMANN CREEK.g01 (geometry) --- (continued)

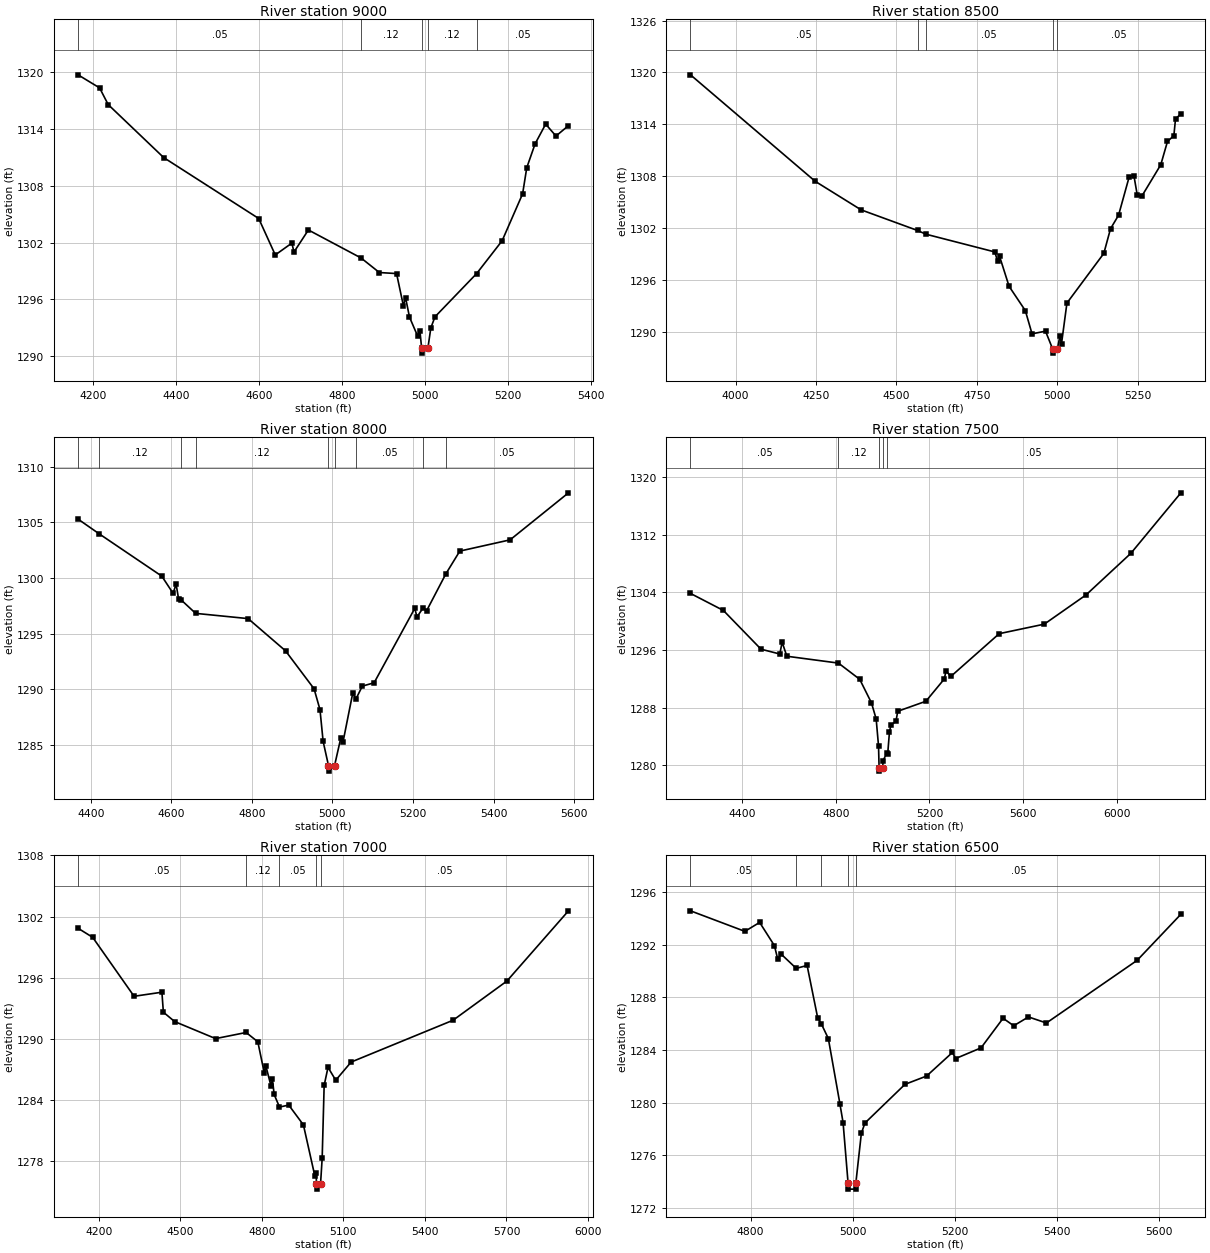
Type RM Length L Ch R = 1,9000,500,500,500
BEGIN DESCRIPTION:
BAUMANN CREEK 18.0
END DESCRIPTION:
XS GIS Cut Line= 3
      2753305.72     10276203.12      2752499.68     10275984.74
      2752155.73     10275953.12
#Sta/Elev= 30
  4164.9 1319.74  4216.7 1318.36  4237.5 1316.59  4371.1 1310.99  4599.8 1304.55
  4639.6 1300.70  4679.5 1301.95  4684.7 1301.01  4719.3 1303.34  4846.1 1300.38
  4890.2 1298.84  4931.6 1298.73  4948.0 1295.33  4953.2 1296.19  4962.7 1294.13
  4982.7 1292.08  4987.8 1292.68  4992.0 1290.82  4992.5 1290.32  5006.9 1290.82
  5014.1 1292.99  5024.1 1294.16  5124.3 1298.73  5185.7 1302.20  5235.0 1307.16
  5245.0 1309.92  5265.1 1312.45  5290.5 1314.53  5315.3 1313.27  5345.4 1314.37
#Mann=5,-1,0
  4164.9    0.05       0  4846.1    0.12       0  4992.0    0.07       0
  5006.9    0.12       0  5124.3    0.05       0
Bank Sta=4992,5006.9
Exp/Cntr=0.3,0.1

Type RM Length L Ch R = 1,8500,500,500,500
BEGIN DESCRIPTION:
BAUMANN CREEK 17.0
END DESCRIPTION:
XS GIS Cut Line= 3
      2753355.64     10276153.08      2752424.95     10275494.58
      2752055.67     10275603.12
#Sta/Elev= 30
  3859.9 1319.73  4247.6 1307.42  4390.3 1304.12  4566.0 1301.73  4592.1 1301.30
  4806.3 1299.25  4815.0 1298.16  4821.1 1298.73  4850.7 1295.27  4901.1 1292.47
  4922.0 1289.78  4963.9 1290.09  4985.9 1288.05  4986.4 1287.55  5000.9 1288.05
  5008.5 1289.48  5013.7 1288.65  5030.5 1293.34  5145.2 1299.08  5166.0 1301.93
  5191.0 1303.49  5224.3 1307.96  5239.0 1308.03  5249.4 1305.79  5262.9 1305.67
  5322.3 1309.33  5343.2 1312.03  5363.0 1312.69  5368.2 1314.64  5384.9 1315.21
#Mann=5,-1,0
  3859.9    0.05       0  4566.0    0.12       0  4592.1    0.05       0
  4985.9    0.05       0  5000.9    0.05       0
Bank Sta=4985.9,5000.9
Exp/Cntr=0.3,0.1

Type RM Length L Ch R = 1,8000,500,500,500
BEGIN DESCRIPTION:
BAUMANN CREEK 16.0
END DESCRIPTION:
XS GIS Cut Line= 3
      2753105.71     10275403.13      2752597.08     10275028.84
      2752055.69     10275253.11
#Sta/Elev= 30
  4368.5 1305.29  4420.1 1303.99  4576.4 1300.17  4604.4 1298.63  4611.9 1299.45
  4618.1 1298.12  4623.7 1298.06  4660.4 1296.83  4790.7 1296.36  4883.5 1293.47
  4954.4 1290.06  4969.1 1288.19  4976.9 1285.34  4990.2 1283.17  4990.7 1282.67
  5005.3 1283.17  5021.0 1285.68  5026.4 1285.31  5050.3 1289.65  5058.7 1289.17
  5074.2 1290.30  5103.5 1290.60  5204.4 1297.28  5209.9 1296.51  5224.6 1297.29
  5233.7 1297.06  5281.8 1300.39  5316.2 1302.42  5441.1 1303.43  5586.0 1307.65
#Mann=9,-1,0
  4368.5    0.05       0  4420.1    0.12       0  4623.7    0.05       0
  4660.4    0.12       0  4990.2    0.07       0  5005.3    0.12       0
  5058.7    0.05       0  5224.6    0.12       0  5281.8    0.05       0
Bank Sta=4990.2,5005.3
Exp/Cntr=0.3,0.1

Type RM Length L Ch R = 1,7500,500,500,500
BEGIN DESCRIPTION:
BAUMANN CREEK 15.0
END DESCRIPTION:
XS GIS Cut Line= 3
      2753505.64     10274603.11      2752688.39     10274545.16
      2751705.68     10275353.11
#Sta/Elev= 30
  4180.7 1303.84  4321.0 1301.48  4481.4 1296.11  4561.6 1295.44  4571.6 1297.08
  4591.7 1295.13  4811.7 1294.18  4902.5 1291.93  4952.6 1288.66  4972.6 1286.43
  4982.7 1282.69  4985.1 1279.70  4985.6 1279.20  5000.3 1279.70  5002.3 1280.65
  5017.3 1281.70  5021.7 1281.55  5029.4 1284.69  5036.0 1285.63  5056.8 1286.09
  5064.7 1287.50  5184.7 1288.89  5262.7 1291.96  5270.6 1293.07  5291.4 1292.34
  5497.3 1298.26  5689.6 1299.58  5867.5 1303.63  6059.1 1309.41  6272.2 1317.79
#Mann=5,-1,0
  4180.7    0.05       0  4811.7    0.12       0  4985.1    0.07       0
  5000.3    0.12       0  5017.3    0.05       0
Bank Sta=4985.1,5000.3
Exp/Cntr=0.3,0.1

Type RM Length L Ch R = 1,7000,500,500,500
BEGIN DESCRIPTION:
BAUMANN CREEK 14.0
END DESCRIPTION:
XS GIS Cut Line= 3
      2753355.69     10274403.11      2752541.90     10274078.08
      2751855.68     10274703.11
#Sta/Elev= 30
  4123.7 1300.86  4177.5 1299.97  4329.8 1294.19  4432.2 1294.59  4437.6 1292.63
  4479.1 1291.71  4629.8 1290.04  4742.1 1290.64  4785.1 1289.73  4809.3 1286.63
  4814.7 1287.36  4833.6 1285.40  4839.0 1286.04  4845.2 1284.56  4864.9 1283.33
  4899.0 1283.52  4952.9 1281.58  4995.2 1276.54  5000.0 1276.91  5000.7 1275.78
  5001.2 1275.28  5015.9 1275.78  5021.9 1278.30  5029.2 1285.45  5043.4 1287.22
  5071.8 1285.96  5128.5 1287.74  5503.5 1291.84  5701.5 1295.68  5928.2 1302.57
#Mann=5,-1,0
  4123.7    0.05       0  4742.1    0.12       0  4864.9    0.05       0
  5000.7    0.05       0  5015.9    0.05       0
Bank Sta=5000.7,5015.9
Exp/Cntr=0.3,0.1

Type RM Length L Ch R = 1,6500,500,500,500
BEGIN DESCRIPTION:
BAUMANN CREEK 13.0
END DESCRIPTION:
XS GIS Cut Line= 3
      2752505.66     10273503.13      2752256.03     10273699.81
      2751855.69     10274203.10
#Sta/Elev= 30
  4682.2 1294.56  4788.8 1293.00  4817.7 1293.68  4846.6 1291.92  4852.9 1290.93
  4860.4 1291.25  4889.4 1290.19  4910.7 1290.41  4931.5 1286.42  4938.5 1285.98
  4952.3 1284.86  4974.9 1279.92  4981.2 1278.47  4990.9 1273.92  4991.4 1273.42
  5005.8 1273.42  5006.3 1273.92  5017.0 1277.66  5024.0 1278.44  5102.5 1281.38
  5144.8 1282.01  5195.4 1283.80  5201.8 1283.34  5251.5 1284.15  5294.7 1286.40
  5315.5 1285.83  5344.4 1286.50  5379.6 1286.04  5557.4 1290.80  5643.1 1294.30
#Mann=5,-1,0
  4682.2    0.05       0  4889.4    0.12       0  4938.5    0.05       0
  4990.9    0.05       0  5006.3    0.05       0
Bank Sta=4990.9,5006.3
Exp/Cntr=0.3,0.1

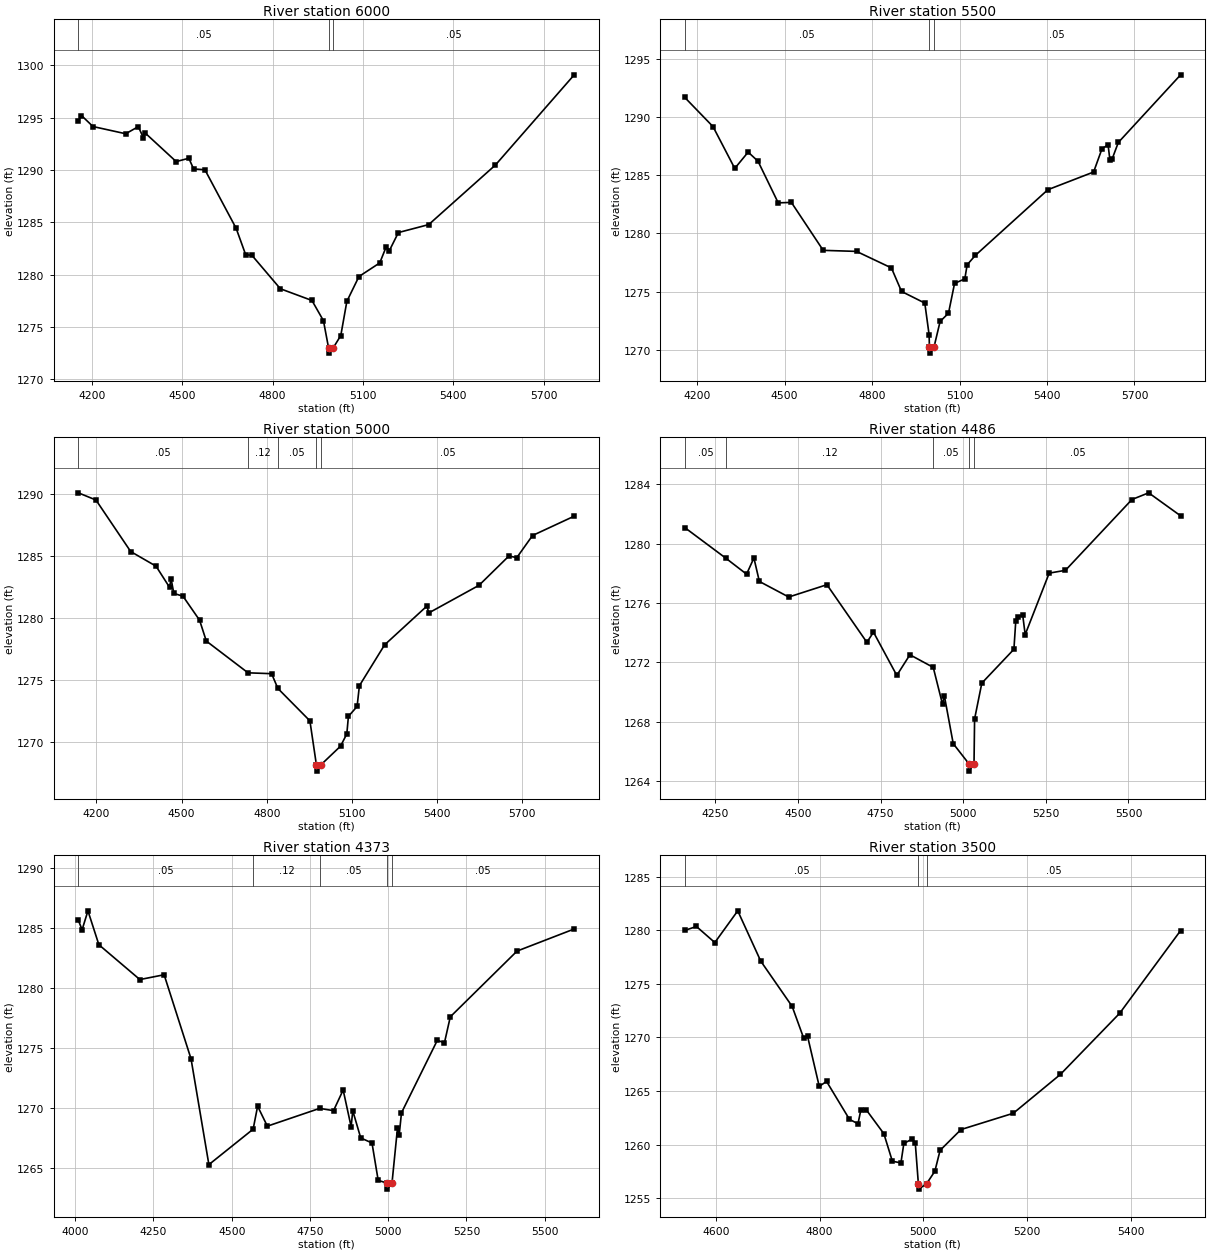
Type RM Length L Ch R = 1,6000,500,500,500
BEGIN DESCRIPTION:
BAUMANN CREEK 12.0
END DESCRIPTION:
XS GIS Cut Line= 3
      2752605.71     10273253.10      2751799.26     10273507.08
      2751705.69     10274303.10
#Sta/Elev= 30
  4154.5 1294.68  4165.0 1295.19  4203.1 1294.14  4311.8 1293.45  4353.7 1294.13
  4370.2 1293.09  4375.4 1293.55  4479.5 1290.79  4521.5 1291.11  4537.3 1290.09
  4574.9 1290.01  4678.7 1284.41  4710.2 1281.90  4731.2 1281.83  4825.5 1278.64
  4930.4 1277.52  4968.6 1275.59  4985.6 1272.99  4986.1 1272.49  5001.0 1272.99
  5026.2 1274.17  5046.4 1277.44  5086.6 1279.81  5155.6 1281.11  5177.2 1282.66
  5187.3 1282.27  5217.5 1284.01  5318.2 1284.77  5539.7 1290.46  5801.5 1299.08
#Mann=3,-1,0
  4154.5    0.05       0  4985.6    0.05       0  5001.0    0.05       0
Bank Sta=4985.6,5001
Exp/Cntr=0.3,0.1

Type RM Length L Ch R = 1,5500,500,500,500
BEGIN DESCRIPTION:
BAUMANN CREEK 11.0
END DESCRIPTION:
XS GIS Cut Line= 3
      2752355.65     10273303.10      2751542.08     10273083.04
      2751005.70     10273753.10
#Sta/Elev= 30
  4157.2 1291.68  4254.2 1289.17  4328.8 1285.58  4374.7 1286.98  4408.5 1286.20
  4477.9 1282.62  4523.0 1282.66  4632.2 1278.54  4746.6 1278.45  4866.2 1277.03
  4900.9 1275.01  4980.7 1274.01  4995.5 1271.29  4996.6 1270.21  4997.1 1269.71
  5012.1 1270.21  5033.2 1272.43  5062.0 1273.14  5082.8 1275.70  5118.0 1276.09
  5126.0 1277.30  5153.8 1278.10  5402.9 1283.75  5559.8 1285.27  5588.6 1287.27
  5609.4 1287.61  5615.8 1286.29  5623.8 1286.42  5644.6 1287.81  5858.3 1293.62
#Mann=3,-1,0
  4157.2    0.05       0  4996.6    0.03       0  5012.1    0.05       0
Bank Sta=4996.6,5012.1
Exp/Cntr=0.3,0.1

Type RM Length L Ch R = 1,5000,514,514,514
BEGIN DESCRIPTION:
BAUMANN CREEK 10.0
END DESCRIPTION:
XS GIS Cut Line= 3
      2752155.68     10272953.11      2751359.60     10272618.11
      2750955.69     10273403.10
#Sta/Elev= 30
  4136.3 1290.06  4198.4 1289.48  4320.7 1285.33  4410.0 1284.15  4457.5 1282.45
  4462.9 1283.14  4472.6 1281.96  4504.9 1281.73  4563.3 1279.80  4587.0 1278.12
  4733.9 1275.56  4817.0 1275.49  4839.1 1274.30  4951.9 1271.69  4974.8 1268.14
  4975.3 1267.64  4990.3 1268.14  5059.7 1269.65  5081.9 1270.64  5087.5 1272.05
  5118.1 1272.85  5126.2 1274.52  5214.9 1277.81  5364.5 1280.95  5370.2 1280.38
  5547.5 1282.61  5652.8 1284.97  5680.6 1284.84  5735.9 1286.62  5882.8 1288.18
#Mann=5,-1,0
  4136.3    0.05       0  4733.9    0.12       0  4839.1    0.05       0
  4974.8    0.03       0  4990.3    0.05       0
Bank Sta=4974.8,4990.3
Exp/Cntr=0.3,0.1

Type RM Length L Ch R = 1,4486,113,113,113
BEGIN DESCRIPTION:
Mapping XS 9d483a97
END DESCRIPTION:
XS GIS Cut Line= 5
      2751875.78     10272474.90      2751699.96     10272131.51
      2751331.84     10272090.30      2751106.58     10272161.73
      2750689.83     10272452.35
#Sta/Elev= 30
  4157.3 1281.08  4282.6 1279.00  4344.4 1277.94  4366.6 1279.03  4383.1 1277.45
  4472.0 1276.40  4587.6 1277.23  4708.4 1273.35  4728.5 1274.03  4799.0 1271.12
  4838.7 1272.51  4909.3 1271.66  4937.5 1269.16  4942.8 1269.76  4969.8 1266.52
  5017.1 1265.17  5017.6 1264.67  5032.7 1265.17  5034.4 1268.18  5056.3 1270.60
  5153.4 1272.88  5159.0 1274.77  5165.1 1275.04  5179.9 1275.21  5187.5 1273.87
  5260.2 1278.01  5309.4 1278.20  5510.6 1282.97  5561.2 1283.42  5657.9 1281.87
#Mann=5,-1,0
  4157.3    0.05       0  4282.6    0.12       0  4909.3    0.05       0
  5017.1    0.03       0  5032.7    0.05       0
Bank Sta=5017.1,5032.7
Exp/Cntr=0.3,0.1

Type RM Length L Ch R = 1,4373,873,873,873
BEGIN DESCRIPTION:
Mapping XS 38e61024
END DESCRIPTION:
XS GIS Cut Line= 6
      2752164.20     10271664.50      2751881.28     10271779.87
      2751477.44     10271919.97      2751164.27     10272032.61
      2750829.11     10272120.52      2750722.00     10272255.10
#Sta/Elev= 30
  4009.9 1285.65  4022.0 1284.87  4040.6 1286.44  4075.5 1283.62  4206.5 1280.72
  4284.0 1281.12  4370.0 1274.12  4427.0 1265.32  4568.4 1268.27  4582.7 1270.18
  4613.8 1268.52  4780.9 1270.00  4825.2 1269.81  4856.0 1271.53  4881.4 1268.48
  4886.7 1269.80  4912.1 1267.54  4948.1 1267.12  4967.9 1264.01  4996.4 1263.78
  4996.9 1263.28  5012.0 1263.78  5029.6 1268.37  5034.9 1267.76  5042.3 1269.63
  5156.9 1275.67  5179.5 1275.45  5198.3 1277.62  5411.5 1283.09  5594.2 1284.93
#Mann=5,-1,0
  4009.9    0.05       0  4568.4    0.12       0  4780.9    0.05       0
  4996.4    0.03       0  5012.0    0.05       0
Bank Sta=4996.4,5012
Exp/Cntr=0.3,0.1

Type RM Length L Ch R = 1,3500,500,500,500
BEGIN DESCRIPTION:
BAUMANN CREEK 7.0
END DESCRIPTION:
XS GIS Cut Line= 3
      2752005.66     10271053.13      2751597.69     10271265.64
      2751105.65     10271203.11
#Sta/Elev= 30
  4540.0 1279.98  4562.5 1280.35  4598.0 1278.85  4642.2 1281.81  4686.5 1277.12
  4747.1 1272.89  4769.2 1269.94  4776.8 1270.10  4799.3 1265.43  4813.4 1265.89
  4857.6 1262.35  4874.0 1261.94  4879.7 1263.27  4889.5 1263.27  4923.9 1261.01
  4940.3 1258.44  4956.8 1258.29  4962.4 1260.10  4978.9 1260.53  4984.5 1260.11
  4990.4 1256.34  4990.9 1255.84  5006.2 1256.34  5022.2 1257.51  5032.3 1259.46
  5072.6 1261.40  5173.4 1262.92  5264.1 1266.54  5378.5 1272.25  5496.0 1279.97
#Mann=3,-1,0
  4540.0    0.05       0  4990.4    0.05       0  5006.2    0.05       0
Bank Sta=4990.4,5006.2
Exp/Cntr=0.3,0.1

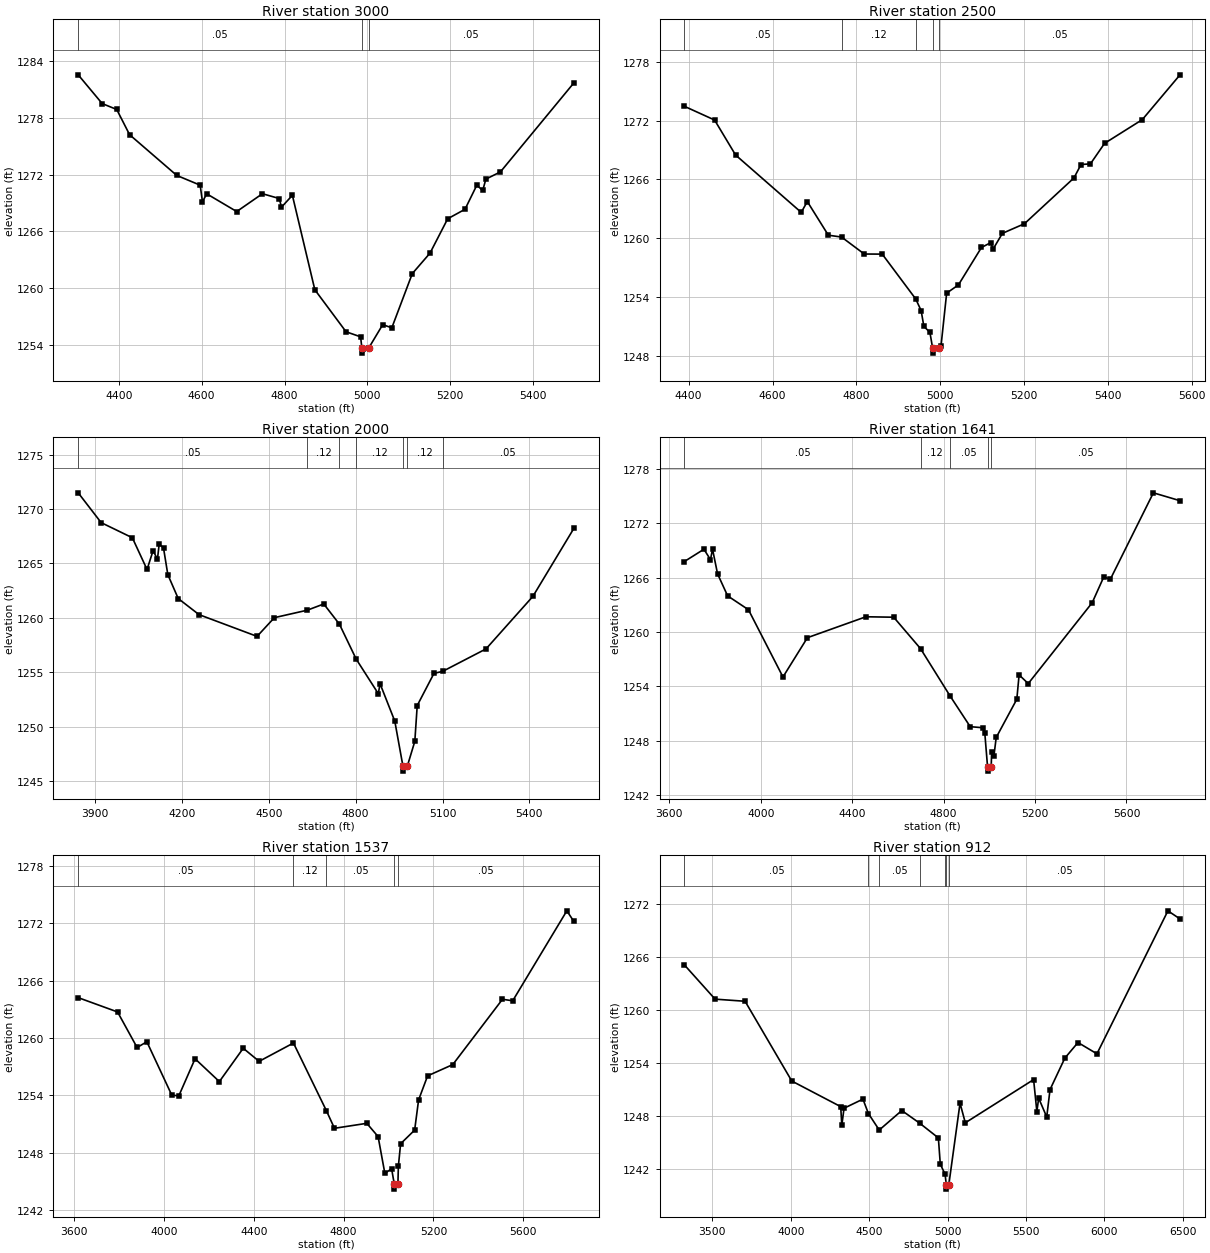
Type RM Length L Ch R = 1,3000,500,500,500
BEGIN DESCRIPTION:
BAUMANN CREEK 6.0
END DESCRIPTION:
XS GIS Cut Line= 3
      2752055.73     10271003.12      2751380.71     10270825.08
      2751055.65     10271203.15
#Sta/Elev= 30
  4301.9 1282.51  4359.8 1279.48  4394.9 1278.86  4426.0 1276.20  4539.8 1271.91
  4596.4 1270.88  4601.9 1269.13  4612.2 1269.97  4684.6 1268.10  4746.7 1269.98
  4787.5 1269.47  4792.6 1268.56  4819.0 1269.81  4873.2 1259.86  4948.6 1255.43
  4983.7 1254.90  4986.9 1253.68  4987.4 1253.18  5002.8 1253.68  5037.1 1256.18
  5059.1 1255.85  5108.5 1261.56  5151.3 1263.72  5194.0 1267.34  5235.8 1268.34
  5264.3 1270.88  5278.5 1270.32  5286.2 1271.52  5321.3 1272.28  5498.6 1281.66
#Mann=3,-1,0
  4301.9    0.05       0  4986.9    0.03       0  5002.8    0.05       0
Bank Sta=4986.9,5002.8
Exp/Cntr=0.3,0.1

Type RM Length L Ch R = 1,2500,500,500,500
BEGIN DESCRIPTION:
BAUMANN CREEK 5.0
END DESCRIPTION:
XS GIS Cut Line= 3
      2751905.67     10270703.10      2751414.42     10270340.97
      2750905.68     10270603.11
#Sta/Elev= 30
  4389.7 1273.46  4461.8 1272.06  4511.9 1268.49  4668.5 1262.64  4683.1 1263.74
  4733.2 1260.31  4764.8 1260.12  4818.9 1258.39  4861.8 1258.38  4941.8 1253.80
  4954.6 1252.62  4961.2 1251.00  4975.5 1250.41  4982.1 1248.78  4982.6 1248.28
  4998.0 1248.78  5002.1 1249.03  5015.5 1254.40  5043.6 1255.24  5098.6 1259.06
  5120.7 1259.55  5126.3 1258.89  5148.5 1260.50  5201.1 1261.48  5319.2 1266.15
  5336.1 1267.52  5358.6 1267.59  5392.3 1269.68  5482.3 1272.10  5572.3 1276.67
#Mann=5,-1,0
  4389.7    0.05       0  4764.8    0.12       0  4941.8    0.05       0
  4982.1    0.05       0  4998.0    0.05       0
Bank Sta=4982.1,4998
Exp/Cntr=0.3,0.1

Type RM Length L Ch R = 1,2000,359,359,359
BEGIN DESCRIPTION:
BAUMANN CREEK 4.0
END DESCRIPTION:
XS GIS Cut Line= 3
      2752305.67     10270503.10      2751348.42     10269850.58
      2750855.67     10270103.12
#Sta/Elev= 30
  3841.5 1271.49  3920.8 1268.75  4028.5 1267.36  4079.3 1264.44  4100.3 1266.18
  4115.2 1265.38  4121.3 1266.77  4136.2 1266.42  4151.1 1263.97  4187.0 1261.77
  4258.9 1260.29  4459.4 1258.29  4519.1 1260.01  4633.0 1260.70  4689.8 1261.27
  4743.9 1259.41  4801.8 1256.20  4878.2 1253.02  4884.2 1253.94  4935.1 1250.50
  4963.0 1246.40  4963.5 1245.90  4978.9 1246.40  5004.3 1248.64  5012.6 1251.93
  5070.5 1254.89  5100.2 1255.07  5250.3 1257.14  5412.2 1261.97  5553.7 1268.22
#Mann=7,-1,0
  3841.5    0.05       0  4633.0    0.12       0  4743.9    0.05       0
  4801.8    0.12       0  4963.0    0.07       0  4978.9    0.12       0
  5100.2    0.05       0
Bank Sta=4963,4978.9
Exp/Cntr=0.3,0.1

Type RM Length L Ch R = 1,1641,104,104,104
BEGIN DESCRIPTION:
Mapping XS 4c0c2599
END DESCRIPTION:
XS GIS Cut Line= 6
      2752257.63     10270274.42      2751697.22     10270016.19
      2751565.35     10269810.15      2751221.96     10269527.19
      2750963.72     10269521.70      2750452.71     10269840.40
#Sta/Elev= 30
  3665.4 1267.77  3751.1 1269.13  3779.6 1267.98  3788.7 1269.13  3810.7 1266.41
  3854.7 1263.98  3945.8 1262.45  4096.9 1255.02  4203.9 1259.36  4459.9 1261.67
  4581.5 1261.62  4698.9 1258.15  4827.2 1252.96  4916.3 1249.53  4973.0 1249.41
  4980.1 1248.82  4992.1 1245.12  4992.6 1244.62  5008.1 1245.12  5010.1 1246.71
  5020.1 1246.33  5030.1 1248.34  5120.2 1252.56  5130.2 1255.25  5170.2 1254.29
  5450.0 1263.22  5500.9 1266.08  5529.0 1265.79  5717.8 1275.36  5834.4 1274.49
#Mann=5,-1,0
  3665.4    0.05       0  4698.9    0.12       0  4827.2    0.05       0
  4992.1    0.03       0  5008.1    0.05       0
Bank Sta=4992.1,5008.1
Exp/Cntr=0.3,0.1

Type RM Length L Ch R = 1,1537,625,625,625
BEGIN DESCRIPTION:
Mapping XS c337a33f
END DESCRIPTION:
XS GIS Cut Line= 6
      2752309.81     10270175.51      2751870.29     10269939.27
      2751474.70     10269521.70      2751265.91     10269428.30
      2750958.23     10269411.81      2750436.28     10269694.76
#Sta/Elev= 30
  3618.4 1264.22  3793.7 1262.72  3880.6 1259.00  3924.1 1259.60  4035.1 1254.01
  4066.5 1253.94  4138.7 1257.82  4246.9 1255.43  4353.2 1258.92  4424.0 1257.55
  4576.8 1259.47  4723.5 1252.38  4759.4 1250.54  4903.4 1251.06  4953.7 1249.67
  4983.8 1245.81  5013.8 1246.31  5025.9 1244.67  5026.4 1244.17  5041.9 1244.67
  5043.9 1246.57  5053.9 1248.92  5116.4 1250.35  5134.0 1253.51  5174.1 1256.03
  5286.2 1257.21  5507.5 1264.05  5553.0 1263.89  5794.0 1273.31  5825.3 1272.20
#Mann=5,-1,0
  3618.4    0.05       0  4576.8    0.12       0  4723.5    0.05       0
  5025.9    0.05       0  5041.9    0.05       0
Bank Sta=5025.9,5041.9
Exp/Cntr=0.3,0.1

Type RM Length L Ch R = 1,912,500,500,500
BEGIN DESCRIPTION:
Mapping XS cdf544b9
END DESCRIPTION:
XS GIS Cut Line= 5
      2752619.82     10270255.24      2751690.99     10269187.53
      2751500.02     10268875.03      2750788.21     10269100.72
      2750345.50     10269552.11
#Sta/Elev= 30
  3321.5 1265.11  3517.4 1261.23  3708.7 1260.99  4006.4 1251.96  4318.4 1249.06
  4325.4 1246.94  4339.6 1248.88  4460.2 1249.91  4494.9 1248.28  4564.1 1246.41
  4708.0 1248.62  4822.3 1247.18  4941.1 1245.52  4953.4 1242.54  4983.7 1241.42
  4991.7 1240.22  4992.2 1239.72  5007.7 1240.22  5079.2 1249.45  5112.9 1247.23
  5548.3 1252.12  5569.1 1248.50  5580.6 1250.02  5632.0 1247.89  5653.0 1250.99
  5747.4 1254.55  5831.3 1256.32  5952.1 1255.04  6404.7 1271.23  6481.9 1270.31
#Mann=7,-1,0
  3321.5    0.05       0  4494.9    0.12       0  4564.1    0.05       0
  4822.3    0.12       0  4983.7    0.05       0  4991.7    0.05       0
  5007.7    0.05       0
Bank Sta=4991.7,5007.7
Exp/Cntr=0.3,0.1

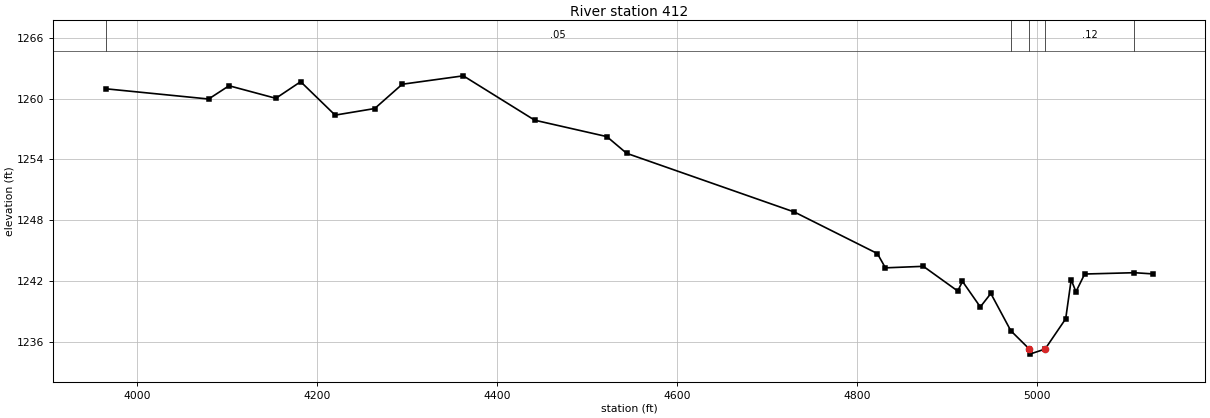
Type RM Length L Ch R = 1,412,0,0,0
BEGIN DESCRIPTION:
BAUMANN CREEK 2.0
END DESCRIPTION:
XS GIS Cut Line= 3
      2752706.62     10269057.32      2752020.85     10268692.73
      2751653.68     10268569.40
#Sta/Elev= 30
  3965.1 1260.96  4079.4 1259.95  4102.1 1261.26  4154.1 1260.02  4181.7 1261.66
  4220.0 1258.36  4264.0 1259.01  4294.6 1261.41  4362.5 1262.24  4441.8 1257.86
  4522.0 1256.24  4544.0 1254.59  4730.5 1248.79  4822.7 1244.69  4831.6 1243.28
  4873.8 1243.43  4912.0 1240.99  4917.3 1241.94  4937.1 1239.42  4948.8 1240.75
  4971.0 1237.07  4991.6 1235.26  4992.1 1234.76  5009.1 1235.26  5032.0 1238.25
  5038.1 1242.10  5043.4 1240.92  5053.1 1242.67  5108.4 1242.80  5129.1 1242.68
#Mann=5,-1,0
  3965.1    0.05       0  4971.0    0.12       0  4991.6    0.07       0
  5009.1    0.12       0  5108.4    0.05       0
Bank Sta=4991.6,5009.1
Exp/Cntr=0.3,0.1

Chan Stop Cuts=-1