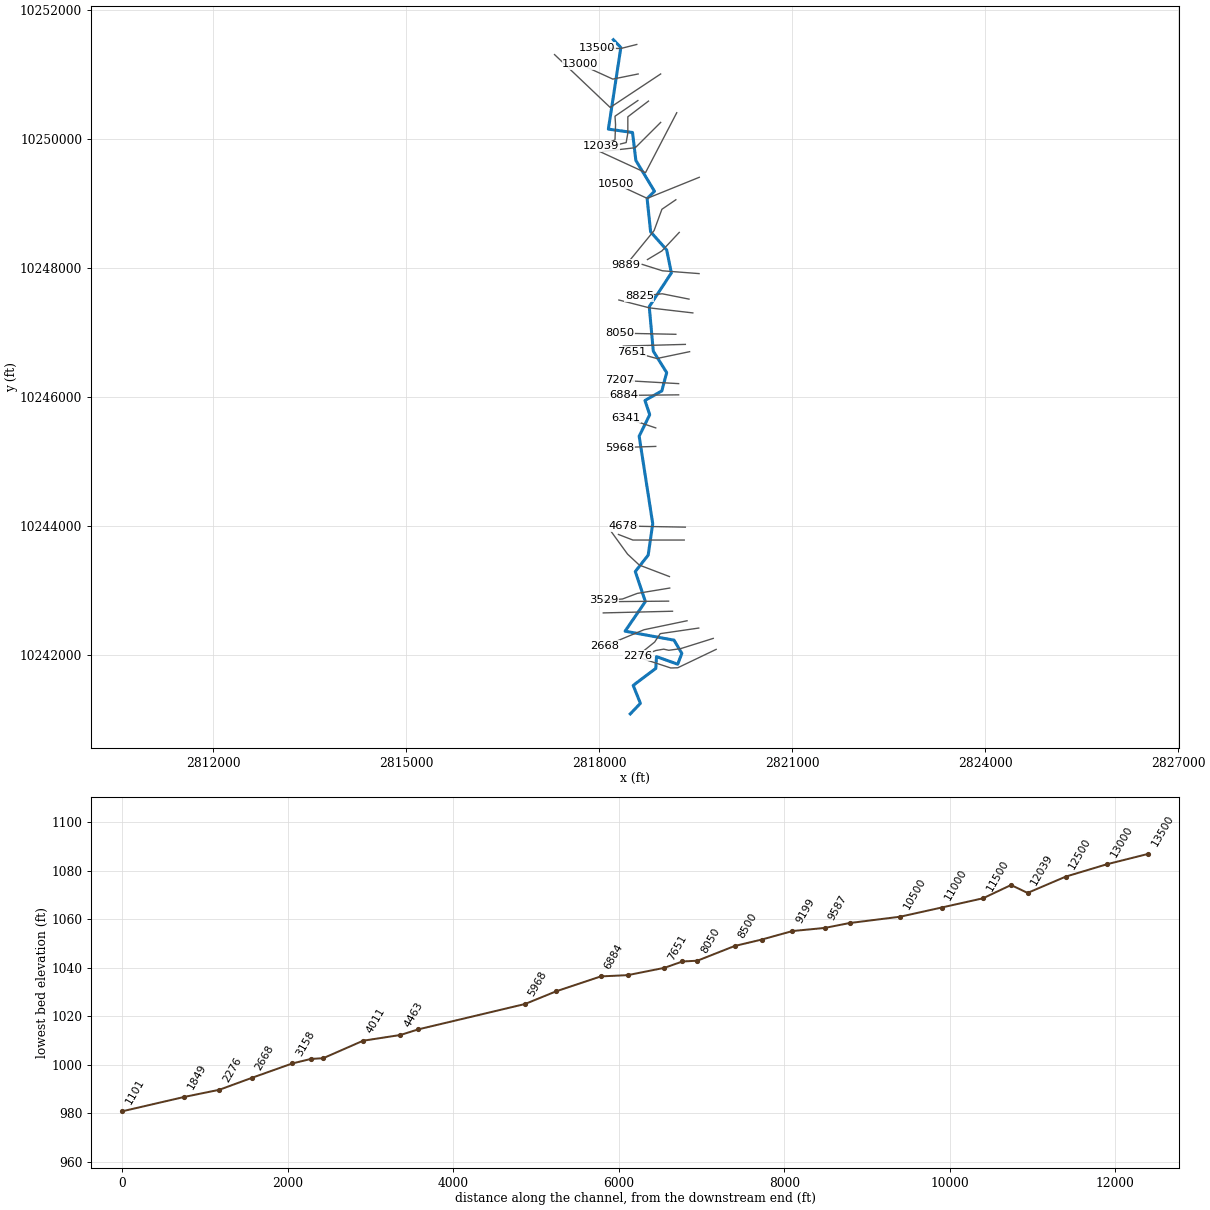
--- BUTTERY CREEK.prj (project) ---

Proj Title=BUTTERY CREEK Base Level Engineering
Current Plan=p01
Default Exp/Contr=0.3,0.1
English Units
Geom File=g01
Flow File=f01
Plan File=p01
Y Axis Title=Elevation
X Axis Title(PF)=Main Channel Distance
X Axis Title(XS)=Station
BEGIN DESCRIPTION:
BUTTERY CREEK
END DESCRIPTION:
DSS Export Rating Curves= 0
DSS Export Rating Curve Sorted= 0
DSS Export Volume Flow Curves= 0
DXF OffsetX= 0
DXF OffsetY= 0
DXF ScaleX= 1
DXF ScaleY= 10

--- BUTTERY CREEK.p01 (plan) ---

Plan Title=Multiple Run
Short Identifier=Multiple
Geom File=g01
Flow File=f01
Subcritical Flow
K Sum by GR= 0
Std Step Tol= 0.01
Critical Tol= 0.01
Num of Std Step Trials= 20
Max Error Tol= 0.3
Flow Tol Ratio= 0.001
Split Flow NTrial= 30
Split Flow Tol= 0.02
Split Flow Ratio= 0.02
Log Output Level= 0
Friction Slope Method= 1
Unsteady Friction Slope Method= 2
Unsteady Bridges Friction Slope Method= 1
Parabolic Critical Depth
Global Vel Dist=  1 , 1 , 1
Global Log Level= 0
CheckData=True
Encroach Param= -1, 0, 0, 0
BEGIN DESCRIPTION:
Multiple Run
END DESCRIPTION:

--- BUTTERY CREEK.f01 (steady flow) ---

Flow Title=Multiple
Number of Profiles=7
Profile Names=10-year,25-year,50-year,1pct_min,100-year,1pct_plu,500-year
River Rch & RM= BUTTERY CREEK,Reach-1,13500
     421     684     752     501     982    1922    1328
River Rch & RM= BUTTERY CREEK,Reach-1,4678
     616    1018    1249     823    1661    3354    2243
River Rch & RM= BUTTERY CREEK,Reach-1,3529
     755    1264    1636     941    2200    5143    2979
River Rch & RM= BUTTERY CREEK,Reach-1,1101
     807    1361    1764    1016    2383    5589    3235
Boundary for River Rch & Prof#=BUTTERY CREEK,Reach-1,1
Up Type=0
Dn Type=3
Dn Slope=0.005
Boundary for River Rch & Prof#=BUTTERY CREEK,Reach-1,2
Up Type=0
Dn Type=3
Dn Slope=0.005
Boundary for River Rch & Prof#=BUTTERY CREEK,Reach-1,3
Up Type=0
Dn Type=3
Dn Slope=0.005
Boundary for River Rch & Prof#=BUTTERY CREEK,Reach-1,4
Up Type=0
Dn Type=3
Dn Slope=0.005
Boundary for River Rch & Prof#=BUTTERY CREEK,Reach-1,5
Up Type=0
Dn Type=3
Dn Slope=0.005
Boundary for River Rch & Prof#=BUTTERY CREEK,Reach-1,6
Up Type=0
Dn Type=3
Dn Slope=0.005
Boundary for River Rch & Prof#=BUTTERY CREEK,Reach-1,7
Up Type=0
Dn Type=3
Dn Slope=0.005

--- BUTTERY CREEK.g01 (geometry) ---

Geom Title=Existing Conditions
Program Version=4.10

River Reach=BUTTERY CREEK   ,Reach-1
Reach XY= 30
        2818220.       10251533.       2818336.5       10251413.
      2818142.75       10250149.      2818517.75       10250097.
        2818570.       10249664.       2818859.5       10249187.
      2818744.75       10249074.      2818799.75       10248558.
        2819049.       10248278.        2819122.       10247922.
      2818778.25       10247401.      2818840.75       10246712.
        2819049.       10246378.        2818973.       10246095.
       2818711.5       10245947.       2818785.5       10245727.
      2818621.25       10245394.      2818832.25       10244039.
       2818761.5       10243553.       2818561.5       10243298.
      2818717.75       10242833.       2818402.5       10242375.
      2819163.25       10242236.       2819284.5       10242031.
       2819220.5       10241863.      2818890.75       10241981.
      2818880.25       10241799.      2818528.25       10241535.
      2818640.75       10241258.      2818483.25       10241094.

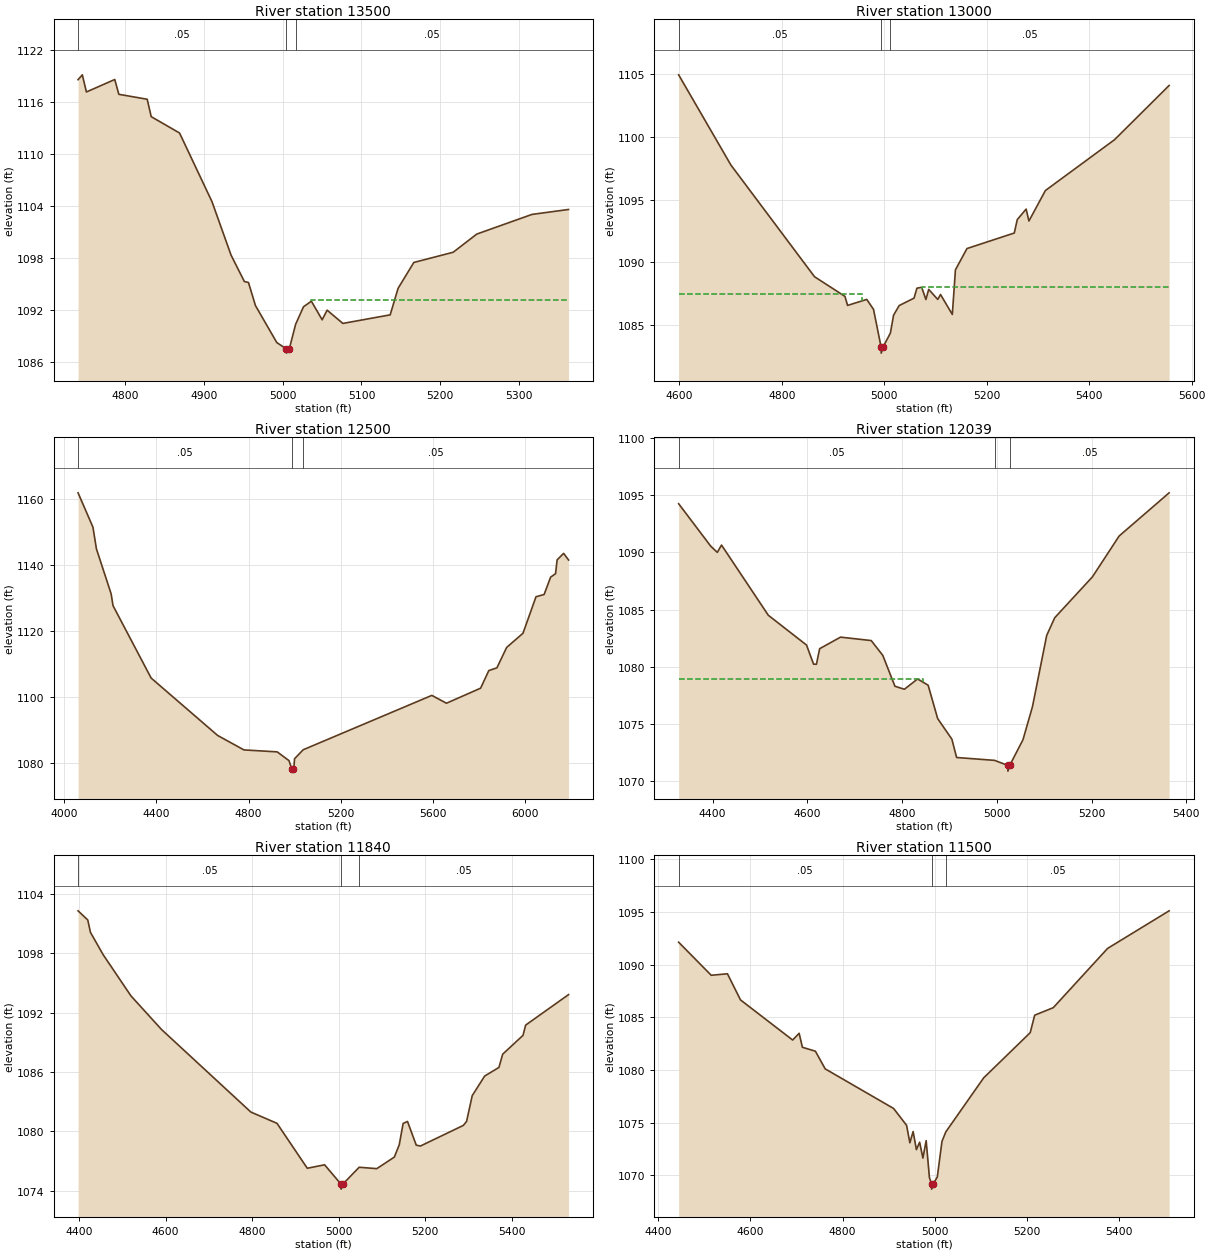
Type RM Length L Ch R = 1 ,13500   ,500,500,500
BEGIN DESCRIPTION:
BUTTERY CREEK 27.0
END DESCRIPTION:
XS GIS Cut Line= 3
      2818584.17     10251459.89      2818332.09     10251396.62
      2817969.26     10251407.75
#Sta/Elev= 30
  4740.1 1118.61  4745.5 1119.17  4750.7 1117.19  4786.7 1118.63  4791.9 1116.92
  4827.9 1116.35    4833 1114.34    4869 1112.45  4910.2 1104.52  4934.4 1098.35
  4951.3  1095.3  4956.5 1095.19  4965.4 1092.52  4992.5 1088.25  5004.4 1087.53
  5004.7 1087.03  5008.4 1087.53  5016.4 1090.36  5026.4 1092.38  5036.4 1093.03
  5050.1 1090.88  5056.4 1091.99  5076.4 1090.46  5136.5 1091.45  5146.5 1094.51
  5166.5  1097.5  5216.5 1098.68  5246.5 1100.78  5316.6 1103.05    5363 1103.62
#Mann= 3 ,-1 , 0
  4740.1     .05       0  5004.4     .07       0  5016.4     .05       0
#XS Ineff= 2 , 0
                         5036.48         1093.12
Permanent Ineff=
       F       F
Bank Sta=5004.4,5008.4
XS Rating Curve= 0 ,0
Exp/Cntr=0.3,0.1

Type RM Length L Ch R = 1 ,13000   ,500,500,500
BEGIN DESCRIPTION:
BUTTERY CREEK 26.0
END DESCRIPTION:
XS GIS Cut Line= 3
      2818605.69     10251003.11      2818212.06     10250923.51
      2817705.68     10251153.11
#Sta/Elev= 30
  4598.4 1104.97  4700.4 1097.77  4863.7 1088.85  4923.1 1087.28  4928.2 1086.56
  4965.7 1087.04  4978.9 1086.24  4993.6 1083.25  4993.9 1082.75  4997.6 1083.25
  5011.8 1084.35    5018 1085.78    5029 1086.55    5058 1087.14  5063.5 1087.93
  5072.9 1088.01  5081.1 1087.03  5086.6 1087.84  5104.2 1087.04  5109.7 1087.43
  5132.7 1085.84  5138.8  1089.4  5161.3  1091.1  5253.7 1092.34  5259.5 1093.41
  5276.8 1094.25  5282.3  1093.3  5314.4 1095.73  5449.4 1099.79    5556 1104.12
#Mann= 3 ,-1 , 0
  4598.4     .05       0  4993.6     .07       0  5011.8     .05       0
#XS Ineff= 2 , 0
         4955.68 1087.44 5074.32         1088.04
Permanent Ineff=
       F       F
Bank Sta=4993.6,4997.6
XS Rating Curve= 0 ,0
Exp/Cntr=0.3,0.1

Type RM Length L Ch R = 1 ,12500   ,461,461,461
BEGIN DESCRIPTION:
BUTTERY CREEK 25.0
END DESCRIPTION:
XS GIS Cut Line= 3
      2818955.69     10251003.11      2818170.61     10250484.69
      2817305.66     10251303.14
#Sta/Elev= 30
  4059.2 1161.73  4123.9 1151.36    4139  1144.8    4203 1131.19  4211.2 1127.62
  4376.8 1105.75  4665.8  1088.4  4780.1 1084.03  4924.6 1083.44  4975.8  1080.8
  4988.9 1078.12  4989.1 1077.62  4992.9 1078.12  4996.9 1078.34    5000 1081.36
  5037.6 1084.08  5596.7 1100.51  5660.2 1098.14  5808.7 1102.69  5844.3 1108.01
  5879.5 1108.84  5921.9 1115.01  5992.7 1119.28  6049.4 1130.33  6084.6    1131
  6112.9 1136.25  6134.3 1137.28  6141.2 1141.47  6169.5 1143.43  6190.8 1141.43
#Mann= 3 ,-1 , 0
  4059.2     .05       0  4988.9     .05       0  5037.6     .05       0
Bank Sta=4988.9,4992.9
XS Rating Curve= 0 ,0
Exp/Cntr=0.3,0.1

Type RM Length L Ch R = 1 ,12039   ,199,199,199
BEGIN DESCRIPTION:
Mapping XS 165cc3e3
END DESCRIPTION:
XS GIS Cut Line= 5
      2818601.49     10250591.81      2818245.61     10250348.77
      2818254.29     10250218.56      2818245.61     10249984.19
       2818029.6      10249880.5
#Sta/Elev= 30
  4328.2 1094.25  4395.8 1090.55  4409.8    1090  4418.7 1090.64  4517.5 1084.51
  4598.2 1081.91  4613.1 1080.24  4619.1 1080.23  4625.9 1081.59    4670  1082.6
  4734.8  1082.3  4759.2 1081.01  4784.9 1078.31  4804.9 1078.05  4832.7 1078.95
    4855  1078.4  4875.1 1075.49  4905.1 1073.69  4915.1 1072.09  4995.2 1071.84
  5023.2  1071.4  5023.4  1070.9  5027.2  1071.4  5055.2 1073.64  5075.2 1076.52
  5105.3 1082.75  5122.2 1084.29  5201.8 1087.86  5258.3 1091.43  5363.8  1095.2
#Mann= 3 ,-1 , 0
  4328.2     .05       0  4995.2     .07       0  5027.2     .05       0
#XS Ineff= 2 , 0
         4845.14 1078.94
Permanent Ineff=
       F       F
Bank Sta=5023.2,5027.2
XS Rating Curve= 0 ,0
Exp/Cntr=0.3,0.1

Type RM Length L Ch R = 1 ,11840   ,340,340,340
BEGIN DESCRIPTION:
Mapping XS f94131ff
END DESCRIPTION:
XS GIS Cut Line= 5
      2818766.48     10250583.17      2818445.26     10250340.09
      2818445.26     10250088.35      2818419.22     10249940.78
      2818099.36     10249862.98
#Sta/Elev= 30
  4397.7 1102.29  4420.1 1101.37  4426.4 1100.11  4455.5 1097.87    4520 1093.69
  4590.7 1090.29  4797.1 1081.95  4857.5 1080.81  4927.5 1076.27  4967.5 1076.62
  5005.5 1074.66  5005.8 1074.16  5009.5 1074.66  5047.4 1076.37  5088.1 1076.23
  5128.7  1077.4    5140 1078.64    5149  1080.8  5159.1    1081  5179.4  1078.6
  5189.1 1078.52  5288.1  1080.6  5295.6    1081  5308.7 1083.61  5337.4 1085.59
  5370.4 1086.46  5379.1  1087.8    5426  1089.7  5432.2 1090.74  5531.3 1093.82
#Mann= 3 ,-1 , 0
  4397.7     .05       0  5005.5     .07       0  5047.4     .05       0
Bank Sta=5005.5,5009.5
XS Rating Curve= 0 ,0
Exp/Cntr=0.3,0.1

Type RM Length L Ch R = 1 ,11500   ,500,500,500
BEGIN DESCRIPTION:
BUTTERY CREEK 23.0
END DESCRIPTION:
XS GIS Cut Line= 3
      2818955.67      10250253.1      2818561.47     10249861.29
       2818055.7     10249803.11
#Sta/Elev= 30
  4444.2 1092.13  4514.9 1088.99  4550.2 1089.13  4578.5 1086.65  4691.7 1082.84
  4705.8 1083.48  4712.9 1082.15  4741.1 1081.78  4762.4  1080.1  4910.9 1076.34
  4939.1 1074.74  4946.2 1073.08  4953.3 1074.15  4960.4 1072.43  4967.4 1073.14
  4974.5 1071.63  4981.6 1073.28  4988.7 1069.77  4993.2 1069.18  4993.4 1068.68
  4997.2 1069.18  5005.8 1069.84  5015.9 1073.21  5024.3 1074.12  5106.5 1079.25
  5207.5 1083.54  5217.2  1085.2  5257.5 1085.91  5375.5 1091.54  5509.1 1095.11
#Mann= 3 ,-1 , 0
  4444.2     .05       0  4993.2     .07       0  5024.3     .05       0
Bank Sta=4993.2,4997.2
XS Rating Curve= 0 ,0
Exp/Cntr=0.3,0.1

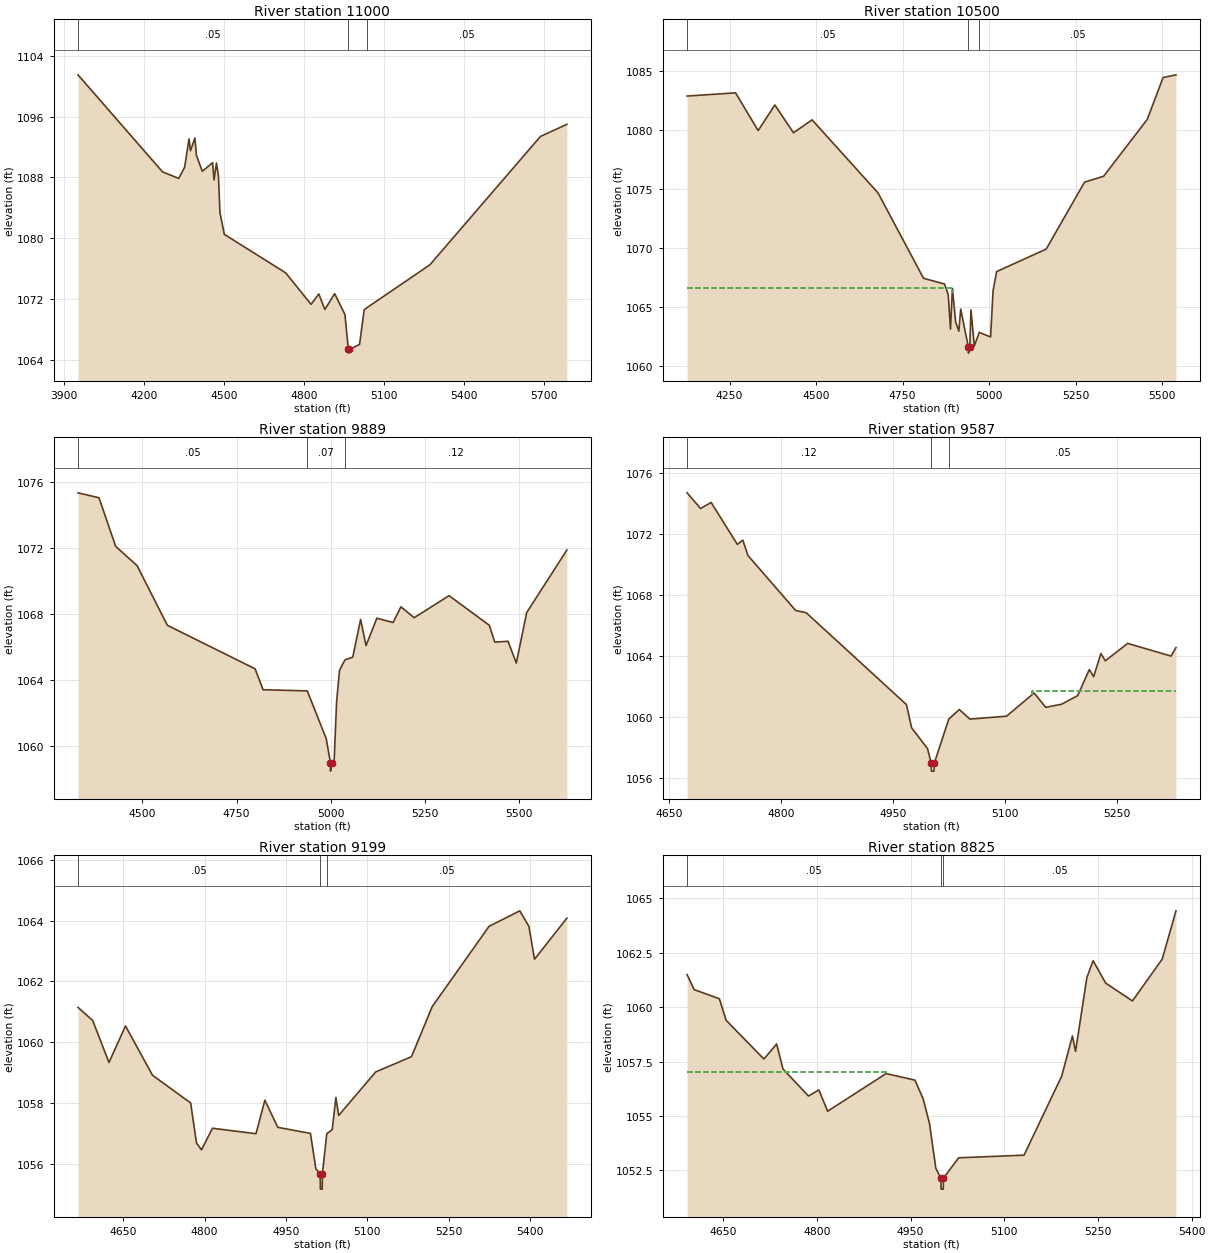
Type RM Length L Ch R = 1 ,11000   ,500,500,500
BEGIN DESCRIPTION:
BUTTERY CREEK 22.0
END DESCRIPTION:
XS GIS Cut Line= 3
       2819205.7     10250403.15       2818720.1     10249475.35
       2818005.7     10249803.11
#Sta/Elev= 30
  3952.8 1101.51    4270 1088.73  4330.6 1087.87  4352.7 1089.35  4369.1 1093.07
  4374.7 1091.52  4391.2  1093.2  4396.8 1090.92  4418.9 1088.81  4457.4 1089.94
    4463 1087.67    4472  1089.9  4479.4 1088.24  4485.1 1083.39  4501.5 1080.51
  4731.6 1075.44  4826.9 1071.29  4855.8 1072.66  4878.4 1070.62  4915.2  1072.7
  4953.7 1069.96  4966.7 1065.37  4966.9 1064.87  4970.7 1065.37  5008.5 1066.01
    5026 1070.58  5037.9 1070.89  5272.4  1076.5    5687  1093.4    5786 1094.99
#Mann= 3 ,-1 , 0
  3952.8     .05       0  4966.7     .07       0  5037.9     .05       0
Bank Sta=4966.7,4970.7
XS Rating Curve= 0 ,0
Exp/Cntr=0.3,0.1

Type RM Length L Ch R = 1 ,10500   ,611,611,611
BEGIN DESCRIPTION:
BUTTERY CREEK 21.0
END DESCRIPTION:
XS GIS Cut Line= 3
      2819555.67     10249403.11      2818746.23      10249076.9
      2818255.68     10249303.12
#Sta/Elev= 30
  4127.3 1082.91  4267.4 1083.18  4332.7 1079.98    4381 1082.15  4434.8 1079.79
  4488.5 1080.89  4679.1 1074.69  4810.7 1067.44  4871.2 1066.96    4882 1066.06
  4888.6 1063.13    4894 1066.58  4903.6 1063.73  4912.7 1062.95  4918.1 1064.83
  4940.3 1061.59  4940.5 1061.09  4944.3 1061.59  4947.7 1064.76  4957.5  1061.7
  4971.8 1062.85  5004.5 1062.46  5011.6 1066.38  5021.9 1068.01  5165.2 1069.92
  5275.9  1075.6    5331  1076.1  5457.1 1080.92    5503 1084.48  5540.2 1084.71
#Mann= 3 ,-1 , 0
  4127.3     .05       0  4940.3     .07       0  4971.8     .05       0
#XS Ineff= 2 , 0
          4895.3 1066.63
Permanent Ineff=
       F       F
Bank Sta=4940.3,4944.3
XS Rating Curve= 0 ,0
Exp/Cntr=0.3,0.1

Type RM Length L Ch R = 1 ,9889    ,302,302,302
BEGIN DESCRIPTION:
Mapping XS fc5ca02a
END DESCRIPTION:
XS GIS Cut Line= 4
      2819191.82     10249055.39      2818974.78      10248907.8
      2818853.25     10248577.94      2818419.96     10248049.33
#Sta/Elev= 30
  4329.1 1075.37  4384.9 1075.07  4429.1 1072.12    4486 1070.95  4566.3 1067.33
  4799.1 1064.69  4820.4 1063.42  4937.6 1063.35  4988.1 1060.44  4999.1 1058.98
  4999.3 1058.48  5003.1 1058.98  5008.9 1059.09  5015.4 1062.66  5023.2  1064.6
  5037.6 1065.23  5058.4  1065.4  5079.2 1067.69  5093.6  1066.1  5122.3 1067.76
  5165.3  1067.5  5186.2 1068.45  5221.3 1067.79  5313.9 1069.13  5420.8 1067.33
  5435.2 1066.31  5470.4 1066.36  5492.4 1065.04  5519.9  1068.1  5626.6  1071.9
#Mann= 3 ,-1 , 0
  4329.1     .05       0  4937.6     .07       0  5037.6     .12       0
Bank Sta=4999.1,5003.1
XS Rating Curve= 0 ,0
Exp/Cntr=0.3,0.1

Type RM Length L Ch R = 1 ,9587    ,388,388,388
BEGIN DESCRIPTION:
Mapping XS 6a1d90e8
END DESCRIPTION:
XS GIS Cut Line= 3
      2819244.44     10248549.81      2818975.36     10248263.37
      2818750.14     10248129.11
#Sta/Elev= 30
  4674.4 1074.69  4692.5 1073.66  4706.6 1074.06  4741.8 1071.31  4749.1 1071.59
    4756 1070.58  4819.9 1066.98  4834.1 1066.83  4968.4 1060.81  4975.3 1059.29
  4996.7 1057.92  5001.6 1056.95  5001.9 1056.45  5005.4 1056.45  5005.6 1056.95
  5025.1 1059.86  5039.2 1060.49  5053.4 1059.86  5102.5 1060.05  5139.5 1061.57
  5155.1 1060.63  5176.5 1060.84  5197.9  1061.4  5213.5 1063.11  5219.3 1062.64
    5229 1064.16  5234.9 1063.68  5264.9 1064.82  5323.1 1063.99  5329.6 1064.55
#Mann= 3 ,-1 , 0
  4674.4     .12       0  5001.6     .07       0  5025.1     .05       0
#XS Ineff= 2 , 0
                         5136.68         1061.68
Permanent Ineff=
       F       F
Bank Sta=5001.6,5005.6
XS Rating Curve= 0 ,0
Exp/Cntr=0.3,0.1

Type RM Length L Ch R = 1 ,9199    ,374,374,374
BEGIN DESCRIPTION:
Mapping XS bd49499c
END DESCRIPTION:
XS GIS Cut Line= 3
      2819552.62     10247911.81      2818984.04     10247955.21
      2818668.95     10248054.49
#Sta/Elev= 30
  4566.9 1061.15  4593.9 1060.72    4624 1059.34  4654.4 1060.54  4704.2 1058.92
  4774.4 1058.01  4785.3 1056.69  4794.5 1056.47  4814.6 1057.18  4894.8    1057
  4911.2  1058.1  4934.9 1057.21  4995.1 1057.01  5005.1 1055.85  5013.1 1055.68
  5013.4 1055.18  5016.9 1055.18  5017.1 1055.68  5025.2    1057  5035.2 1057.13
    5042 1058.19  5047.1  1057.6  5115.4 1059.03  5181.3 1059.53  5219.3 1061.17
  5324.1 1063.81  5380.8 1064.32  5397.5 1063.81  5407.9 1062.73  5467.5 1064.08
#Mann= 3 ,-1 , 0
  4566.9     .05       0  5013.1     .07       0  5025.2     .05       0
Bank Sta=5013.1,5017.1
XS Rating Curve= 0 ,0
Exp/Cntr=0.3,0.1

Type RM Length L Ch R = 1 ,8825    ,325,325,325
BEGIN DESCRIPTION:
Mapping XS 385d0953
END DESCRIPTION:
XS GIS Cut Line= 3
      2819396.38     10247516.84       2818979.7     10247599.31
       2818623.8     10247560.25
#Sta/Elev= 30
  4592.1  1061.5  4603.4 1060.81  4643.8 1060.39  4654.6  1059.4  4715.1 1057.62
  4735.5 1058.31  4745.7 1057.16  4786.5 1055.92  4803.2  1056.2  4817.1 1055.22
  4910.8 1056.95  4956.9 1056.65    4970  1055.8  4980.2 1054.66  4990.4  1052.6
  4998.6 1052.14  4998.8 1051.64  5002.3 1051.64  5002.6 1052.14  5026.9 1053.08
  5131.6  1053.2  5191.9 1056.83  5209.1 1058.68  5214.1 1057.97  5232.2 1061.36
  5242.2 1062.14  5262.3 1061.11  5305.2 1060.29  5352.9 1062.21  5374.9 1064.43
#Mann= 3 ,-1 , 0
  4592.1     .05       0  4998.6     .05       0  5002.6     .05       0
#XS Ineff= 2 , 0
         4911.93 1057.03
Permanent Ineff=
       F       F
Bank Sta=4998.6,5002.6
XS Rating Curve= 0 ,0
Exp/Cntr=0.3,0.1

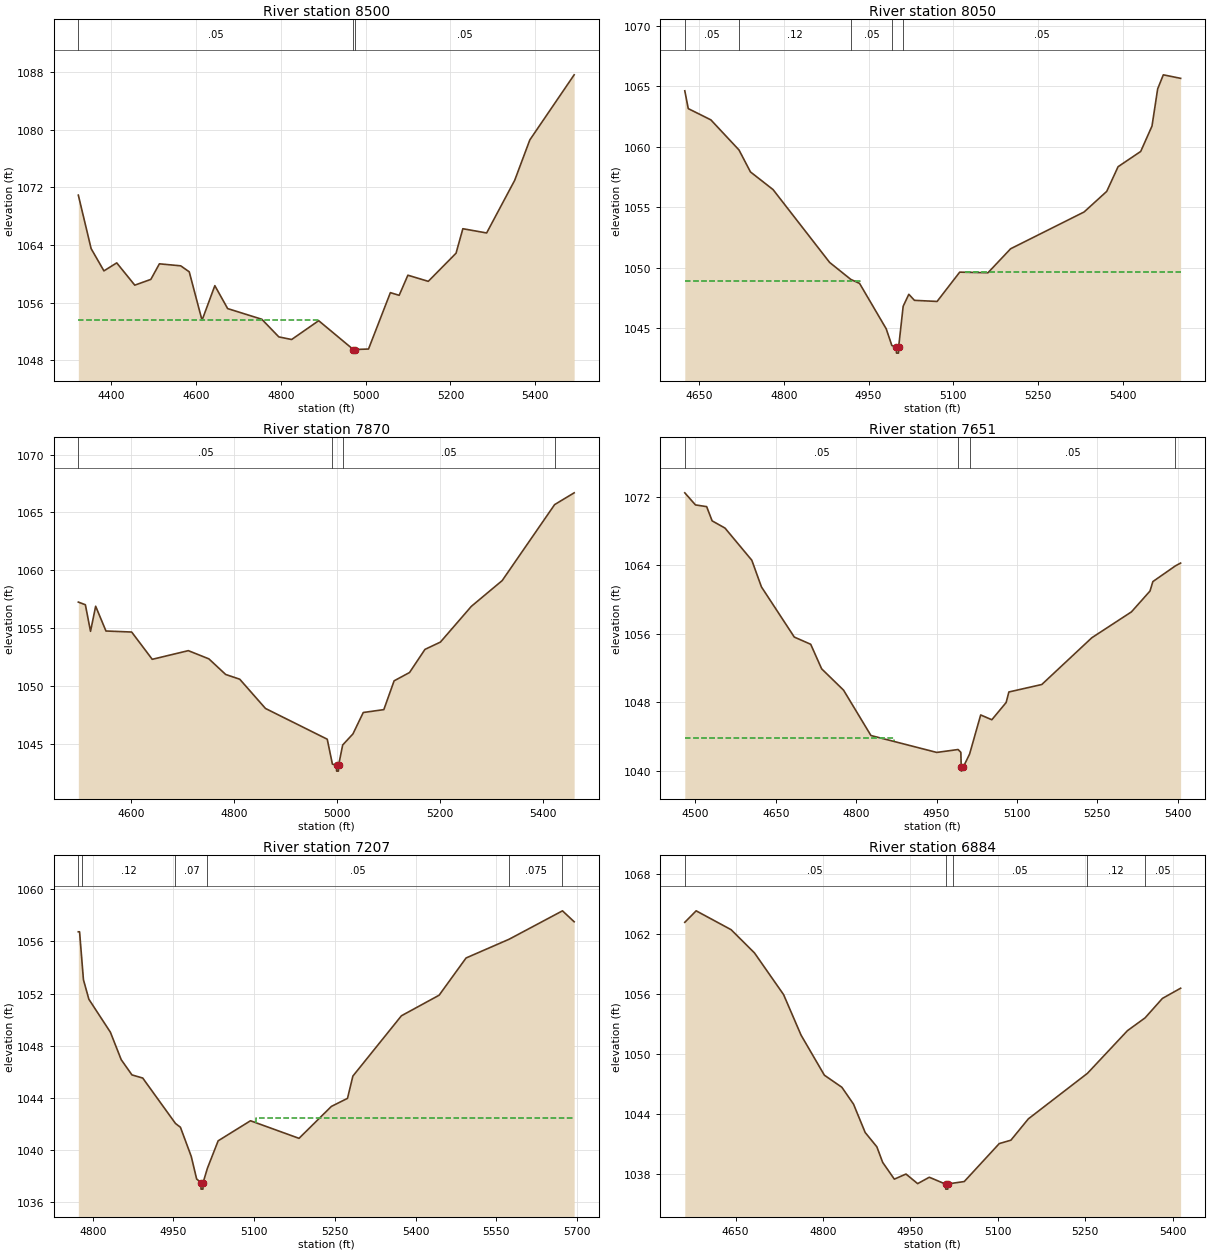
Type RM Length L Ch R = 1 ,8500    ,450,450,450
BEGIN DESCRIPTION:
BUTTERY CREEK 17.0
END DESCRIPTION:
XS GIS Cut Line= 3
      2819455.69     10247303.11      2818782.08     10247381.06
      2818305.67     10247503.12
#Sta/Elev= 30
  4321.9 1070.93  4352.1 1063.51  4382.3 1060.42  4412.5 1061.53  4455.1 1058.44
    4493 1059.24  4513.2  1061.4  4563.5 1061.12  4583.6 1060.29  4613.8 1053.57
    4644 1058.37  4674.2 1055.19  4754.8 1053.71    4795 1051.26  4825.2  1050.9
    4889 1053.51  4970.8 1049.51    4971 1049.01  4974.8 1049.51  5006.6 1049.58
  5058.2  1057.4  5078.9 1057.03  5099.5 1059.82  5147.6 1058.97  5213.1 1062.87
  5229.2 1066.27  5285.3 1065.68  5351.6    1073  5387.2 1078.59  5491.8 1087.62
#Mann= 3 ,-1 , 0
  4321.9     .05       0  4970.8     .05       0  4974.8     .05       0
#XS Ineff= 2 , 0
         4888.86 1053.63
Permanent Ineff=
       F       F
Bank Sta=4970.8,4974.8
XS Rating Curve= 0 ,0
Exp/Cntr=0.3,0.1

Type RM Length L Ch R = 1 ,8050    ,180,180,180
BEGIN DESCRIPTION:
Mapping XS bfdb9bf8
END DESCRIPTION:
XS GIS Cut Line= 2
      2819191.78     10246972.03      2818315.06      10246989.4
#Sta/Elev= 30
  4625.1 1064.61  4631.2 1063.14  4671.2 1062.21    4721 1059.72  4741.2 1057.91
  4781.2 1056.45  4881.3 1050.43  4918.7 1049.03  4934.2  1048.7  4981.3 1044.95
  4991.3 1043.57  4999.3 1043.44  4999.5 1042.94    5003 1042.94  5003.3 1043.44
  5011.3 1046.81  5021.3  1047.8  5031.3  1047.3  5071.3 1047.21  5111.3 1049.63
  5161.3 1049.58  5201.3 1051.56  5331.3  1054.6  5371.3  1056.3  5391.4 1058.34
  5431.4  1059.6  5451.4  1061.7  5461.4 1064.77  5471.4 1065.93    5502 1065.64
#Mann= 5 ,-1 , 0
  4625.1     .05       0    4721     .12       0  4918.7     .05       0
  4991.3     .07       0  5011.3     .05       0
#XS Ineff= 2 , 0
         4934.66 1048.86 5121.02         1049.64
Permanent Ineff=
       F       F
Bank Sta=4999.3,5003.3
XS Rating Curve= 0 ,0
Exp/Cntr=0.3,0.1

Type RM Length L Ch R = 1 ,7870    ,219,219,219
BEGIN DESCRIPTION:
Mapping XS d4d5b659
END DESCRIPTION:
XS GIS Cut Line= 2
      2819339.36     10246815.78      2818375.81     10246789.74
#Sta/Elev= 30
  4496.9 1057.24  4510.6 1057.01  4520.6 1054.71  4530.6 1056.88  4550.6 1054.74
  4600.6 1054.65  4640.6 1052.29  4710.7 1053.04  4750.7 1052.33  4783.3 1050.98
  4810.7 1050.57  4860.7 1048.04  4980.8 1045.38  4990.8 1043.23  4998.8 1043.12
    4999 1042.62  5002.5 1042.62  5002.8 1043.12  5010.8 1044.88  5030.8 1045.84
  5050.8 1047.69  5090.8 1047.94  5110.8 1050.43  5140.8 1051.15  5170.8 1053.15
  5200.8 1053.78  5260.9 1056.87  5320.9  1059.1  5422.8 1065.67  5460.8 1066.69
#Mann= 4 ,-1 , 0
  4496.9     .05       0  4990.8     .07       0  5010.8     .05       0
  5422.8    .075       0
Bank Sta=4998.8,5002.8
XS Rating Curve= 0 ,0
Exp/Cntr=0.3,0.1

Type RM Length L Ch R = 1 ,7651    ,444,444,444
BEGIN DESCRIPTION:
BUTTERY CREEK 15.0
END DESCRIPTION:
XS GIS Cut Line= 3
      2819405.65      10246703.1        2818897.       10246597.
      2818505.73      10246703.1
#Sta/Elev= 30
  4480.4 1072.44  4500.3 1071.03  4521.2 1070.83  4531.4 1069.17  4555.4 1068.33
  4605.4 1064.58  4623.4 1061.47  4684.7 1055.62  4715.3 1054.78  4735.7 1051.92
  4776.6 1049.43  4827.7 1044.14  4950.5 1042.17  4990.3 1042.51  4995.4 1042.18
  4996.1 1040.49  4996.4 1039.99  5000.1 1040.49  5011.7 1041.98  5032.4 1046.54
  5053.2 1045.98  5079.9 1047.99    5085 1049.22  5146.4 1050.09  5239.7 1055.54
  5313.7 1058.56  5348.3 1060.99  5353.6 1062.09  5395.6 1063.92  5405.4 1064.25
#Mann= 4 ,-1 , 0
  4480.4     .05       0  4990.3     .07       0  5011.7     .05       0
  5395.6    .075       0
#XS Ineff= 2 , 0
         4870.45 1043.86
Permanent Ineff=
       F       F
Bank Sta=4996.1,5000.1
XS Rating Curve= 0 ,0
Exp/Cntr=0.3,0.1

Type RM Length L Ch R = 1 ,7207    ,323,323,323
BEGIN DESCRIPTION:
Mapping XS 05b6ed8c
END DESCRIPTION:
XS GIS Cut Line= 2
      2819235.21     10246208.14      2818315.08     10246260.23
#Sta/Elev= 30
  4773.2 1056.74  4775.5 1056.74  4780.7 1054.08  4782.7 1053.06  4792.8 1051.56
  4832.8 1049.03  4852.9 1046.92  4872.9 1045.75  4892.9 1045.51  4953.8 1042.02
    4963 1041.73  4983.1 1039.49  4993.1 1037.76  5001.1 1037.48  5001.3 1036.98
  5004.8 1036.98  5005.1 1037.48  5013.1 1038.58  5033.1 1040.69  5093.2 1042.23
  5183.4 1040.88  5243.5 1043.33  5273.5 1043.95  5283.5 1045.66  5373.7 1050.29
  5443.8 1051.87  5493.9 1054.73    5574 1056.17  5673.1 1058.35  5694.8 1057.51
#Mann= 6 ,-1 , 0
  4773.2     .05       0  4780.7     .12       0  4953.8     .07       0
  5013.1     .05       0    5574    .075       0  5673.1     .05       0
#XS Ineff= 2 , 0
                         5103.86         1042.41
Permanent Ineff=
       F       F
Bank Sta=5001.1,5005.1
XS Rating Curve= 0 ,0
Exp/Cntr=0.3,0.1

Type RM Length L Ch R = 1 ,6884    ,543,543,543
BEGIN DESCRIPTION:
Mapping XS ba845de5
END DESCRIPTION:
XS GIS Cut Line= 2
      2819235.15     10246034.53      2818384.49     10246025.85
#Sta/Elev= 30
  4562.8 1063.19  4582.3 1064.34  4642.3 1062.45  4682.3 1060.13  4732.3 1055.95
  4762.3 1051.89  4802.3 1047.88  4832.3 1046.67  4852.3 1044.98  4872.3 1042.14
  4892.3 1040.71  4902.3 1039.15  4922.3 1037.47  4942.3 1037.98  4962.3 1037.02
  4982.3 1037.66  5010.3 1036.97  5010.5 1036.47    5014 1036.47  5014.3 1036.97
  5022.3 1037.06  5042.3 1037.23  5102.3 1041.03  5122.3 1041.37  5152.3 1043.51
  5253.7 1048.07  5322.3 1052.34  5352.5 1053.62  5382.3 1055.57  5413.5 1056.59
#Mann= 5 ,-1 , 0
  4562.8     .05       0  5010.3     .07       0  5022.3     .05       0
  5253.7     .12       0  5352.5     .05       0
Bank Sta=5010.3,5014.3
XS Rating Curve= 0 ,0
Exp/Cntr=0.3,0.1

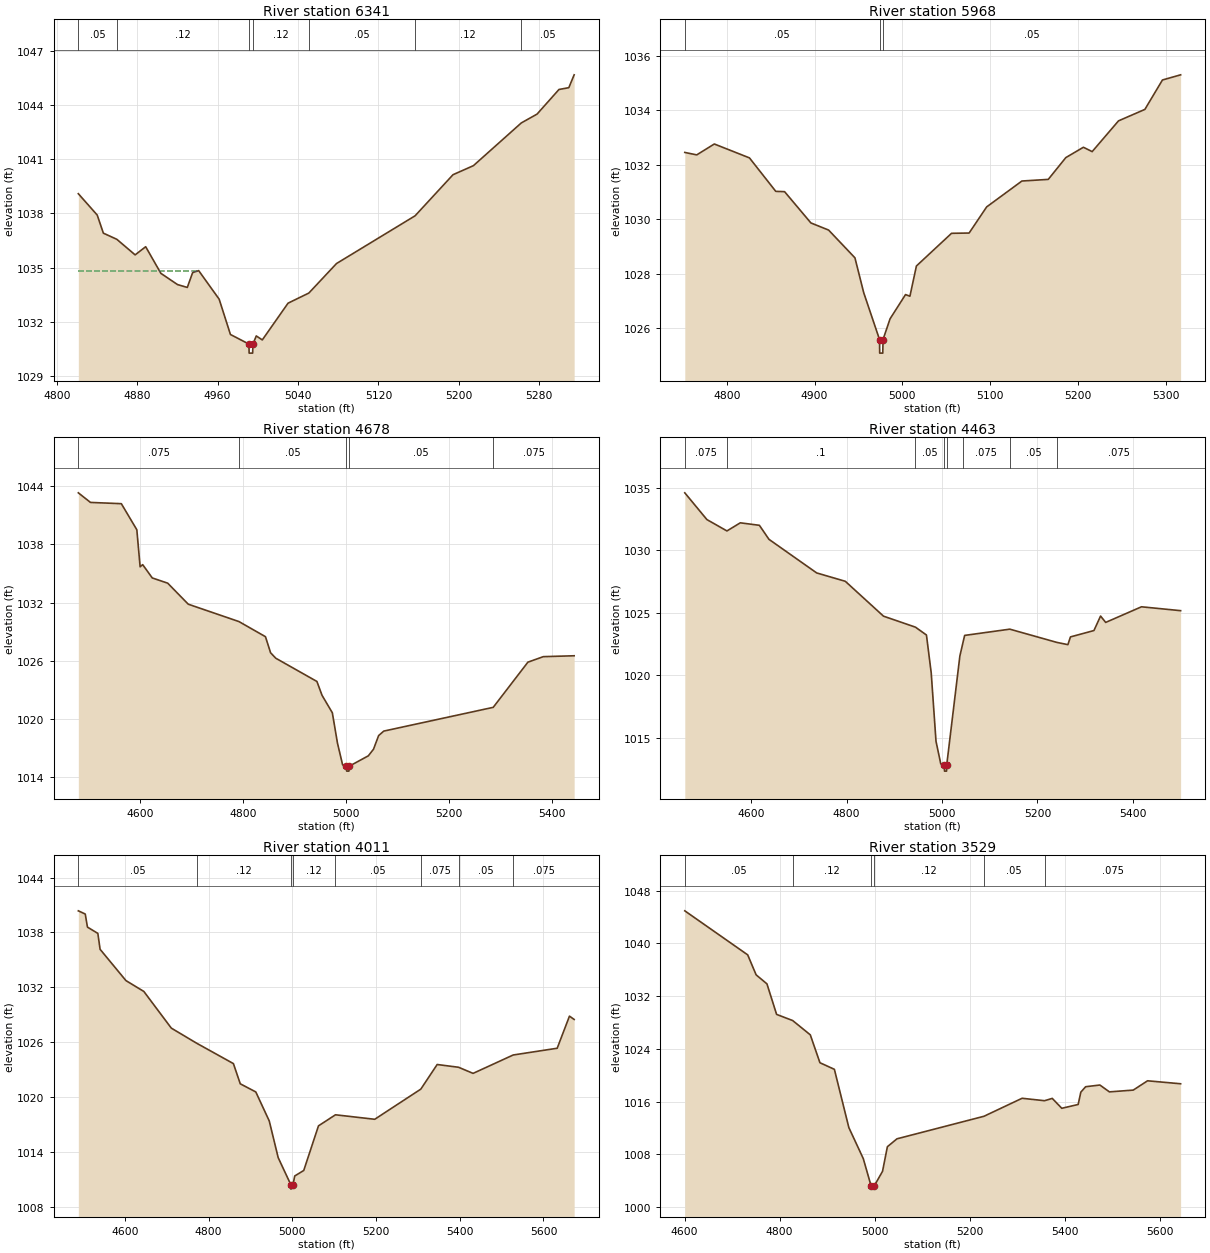
Type RM Length L Ch R = 1 ,6341    ,373,373,373
BEGIN DESCRIPTION:
Mapping XS 89061b35
END DESCRIPTION:
XS GIS Cut Line= 2
      2818879.26     10245522.39      2818411.37     10245678.35
#Sta/Elev= 30
  4821.5 1039.09  4840.3 1037.91  4846.4 1036.91  4859.8 1036.57    4878 1035.71
  4888.5 1036.16  4903.6 1034.69  4920.1 1034.07  4929.9 1033.91  4935.2 1034.73
  4941.2 1034.84  4961.6 1033.26  4972.8 1031.31  4991.2 1030.78  4991.4 1030.28
  4994.9 1030.28  4995.2 1030.78  4998.5 1031.23  5004.5 1031.01  5030.1 1033.04
  5050.8  1033.6  5078.3 1035.23  5156.5 1037.87  5194.2 1040.14  5214.5 1040.64
  5262.1    1043  5277.8 1043.49  5299.6 1044.85  5309.4 1044.95  5314.7 1045.66
#Mann= 7 ,-1 , 0
  4821.5     .05       0  4859.8     .12       0  4991.2     .07       0
  4995.2     .12       0  5050.8     .05       0  5156.5     .12       0
  5262.1     .05       0
#XS Ineff= 2 , 0
         4940.11 1034.84
Permanent Ineff=
       F       F
Bank Sta=4991.2,4995.2
XS Rating Curve= 0 ,0
Exp/Cntr=0.3,0.1

Type RM Length L Ch R = 1 ,5968    ,1290,1290,1290
BEGIN DESCRIPTION:
Mapping XS 8afbac2b
END DESCRIPTION:
XS GIS Cut Line= 2
      2818879.26     10245235.92      2818315.03     10245218.56
#Sta/Elev= 30
  4752.3 1032.45  4765.9 1032.36  4785.9 1032.76  4825.9 1032.25  4855.9 1031.02
  4865.9 1031.01  4895.9 1029.86    4916  1029.6    4946 1028.58    4956  1027.3
    4974 1025.58  4974.2 1025.08  4977.7 1025.08    4978 1025.58    4986 1026.34
  5003.6 1027.23  5008.6 1027.17    5016 1028.28    5056 1029.48    5076 1029.49
    5096 1030.45  5136.1  1031.4  5166.1 1031.46  5186.1 1032.26  5206.1 1032.64
  5216.1 1032.48  5246.1 1033.61  5276.1 1034.03  5296.1 1035.11  5316.8  1035.3
#Mann= 3 ,-1 , 0
  4752.3     .05       0    4974     .05       0    4978     .05       0
Bank Sta=4974,4978
XS Rating Curve= 0 ,0
Exp/Cntr=0.3,0.1

Type RM Length L Ch R = 1 ,4678    ,215,215,215
BEGIN DESCRIPTION:
Mapping XS 718cf9e3
END DESCRIPTION:
XS GIS Cut Line= 2
      2819339.32     10243985.92      2818375.77     10244003.29
#Sta/Elev= 30
  4479.2 1043.33  4502.8 1042.34  4562.8 1042.21  4592.9 1039.52  4599.3  1035.7
  4604.3 1035.92  4622.9 1034.55  4652.9 1034.01  4692.9 1031.84  4791.3 1030.05
  4842.9 1028.49  4852.9 1026.83  4862.9 1026.27  4942.9 1023.87  4952.9 1022.44
  4972.9 1020.64  4982.9  1017.5  4992.9 1015.26  5000.4 1015.12  5000.8 1014.62
  5005.1 1014.62  5005.5 1015.12  5042.9  1016.2  5052.9 1016.88  5062.9 1018.29
  5072.9 1018.75  5285.6  1021.2    5353 1025.86    5383 1026.43  5442.9 1026.52
#Mann= 5 ,-1 , 0
  4479.2    .075       0  4791.3     .05       0  5000.4     .03       0
  5005.5     .05       0  5285.6    .075       0
Bank Sta=5000.4,5005.5
XS Rating Curve= 0 ,0
Exp/Cntr=0.3,0.1

Type RM Length L Ch R = 1 ,4463    ,452,452,452
BEGIN DESCRIPTION:
Mapping XS a81196d3
END DESCRIPTION:
XS GIS Cut Line= 3
      2819321.98     10243786.27      2818523.39     10243786.27
      2818299.19      10243872.5
#Sta/Elev= 30
  4461.2 1034.58  4507.5 1032.44  4549.5 1031.53  4577.5 1032.18  4617.5 1031.98
  4637.5 1030.86  4737.5 1028.17  4797.5  1027.5  4877.5 1024.71  4944.5 1023.83
  4967.5  1023.2  4977.5 1020.16  4987.5  1014.7  4997.5 1012.89  5004.9 1012.81
  5005.3 1012.31  5009.6 1012.31    5010 1012.81  5037.5 1021.52  5043.3 1022.48
  5047.5 1023.17  5142.1 1023.67  5240.8 1022.61  5263.8 1022.43  5269.2 1023.05
  5318.4 1023.56  5332.3 1024.72    5343 1024.21    5418 1025.46    5500 1025.15
#Mann= 8 ,-1 , 0
  4461.2    .075       0  4549.5      .1       0  4944.5     .05       0
  5004.9     .05       0    5010     .05       0  5043.3    .075       0
  5142.1     .05       0  5240.8    .075       0
Bank Sta=5004.9,5010
XS Rating Curve= 0 ,0
Exp/Cntr=0.3,0.1

Type RM Length L Ch R = 1 ,4011    ,482,482,482
BEGIN DESCRIPTION:
Mapping XS e34e47d8
END DESCRIPTION:
XS GIS Cut Line= 4
        2819092.      10243220.7      2818623.22     10243398.66
      2818440.93     10243567.93      2818185.34     10243918.82
#Sta/Elev= 30
    4489 1040.37  4505.5 1040.02  4510.8 1038.59  4535.6  1037.9    4541 1036.16
  4602.7 1032.74  4645.5 1031.55  4711.1 1027.54  4771.6 1025.89  4859.4 1023.66
  4875.8 1021.45  4912.9 1020.56    4945 1017.39  4966.4 1013.37  4996.4 1010.43
  4996.8 1009.93  5001.8 1010.43  5005.9 1011.37  5027.4 1011.97  5062.6 1016.85
  5103.2 1018.06    5197 1017.57  5307.1 1020.87  5346.1 1023.56  5397.1 1023.26
  5431.9 1022.59  5527.6  1024.6  5632.8 1025.34  5662.1 1028.85  5673.3 1028.49
#Mann= 8 ,-1 , 0
    4489     .05       0  4771.6     .12       0  4996.4     .07       0
  5001.8     .12       0  5103.2     .05       0  5307.1    .075       0
  5397.1     .05       0  5527.6    .075       0
Bank Sta=4996.4,5001.8
XS Rating Curve= 0 ,0
Exp/Cntr=0.3,0.1

Type RM Length L Ch R = 1 ,3529    ,147,147,147
BEGIN DESCRIPTION:
Mapping XS e8ff52ed
END DESCRIPTION:
XS GIS Cut Line= 4
      2819096.35     10243042.76      2818592.83     10242960.29
       2818362.8     10242873.49      2818076.31     10242851.78
#Sta/Elev= 30
  4600.5 1044.93  4732.9 1038.25  4750.6 1035.22  4773.4 1033.85  4793.7 1029.22
  4827.5 1028.29  4864.6 1026.12  4884.9 1021.89  4915.3 1020.89  4945.7 1012.06
  4976.1 1007.35  4992.5 1003.22    4993 1002.72  4999.2 1003.22  5016.6 1005.42
  5026.8 1009.15    5047 1010.35  5230.1 1013.77  5310.3  1016.5  5357.5 1016.13
  5373.8 1016.48  5393.8 1014.98  5428.3 1015.56  5433.9 1017.43    5444 1018.25
    5474 1018.51  5494.1 1017.47  5544.2 1017.74  5574.3 1019.15  5643.9  1018.7
#Mann= 6 ,-1 , 0
  4600.5     .05       0  4827.5     .12       0  4992.5     .07       0
  4999.2     .12       0  5230.1     .05       0  5357.5    .075       0
Bank Sta=4992.5,4999.2
XS Rating Curve= 0 ,0
Exp/Cntr=0.3,0.1

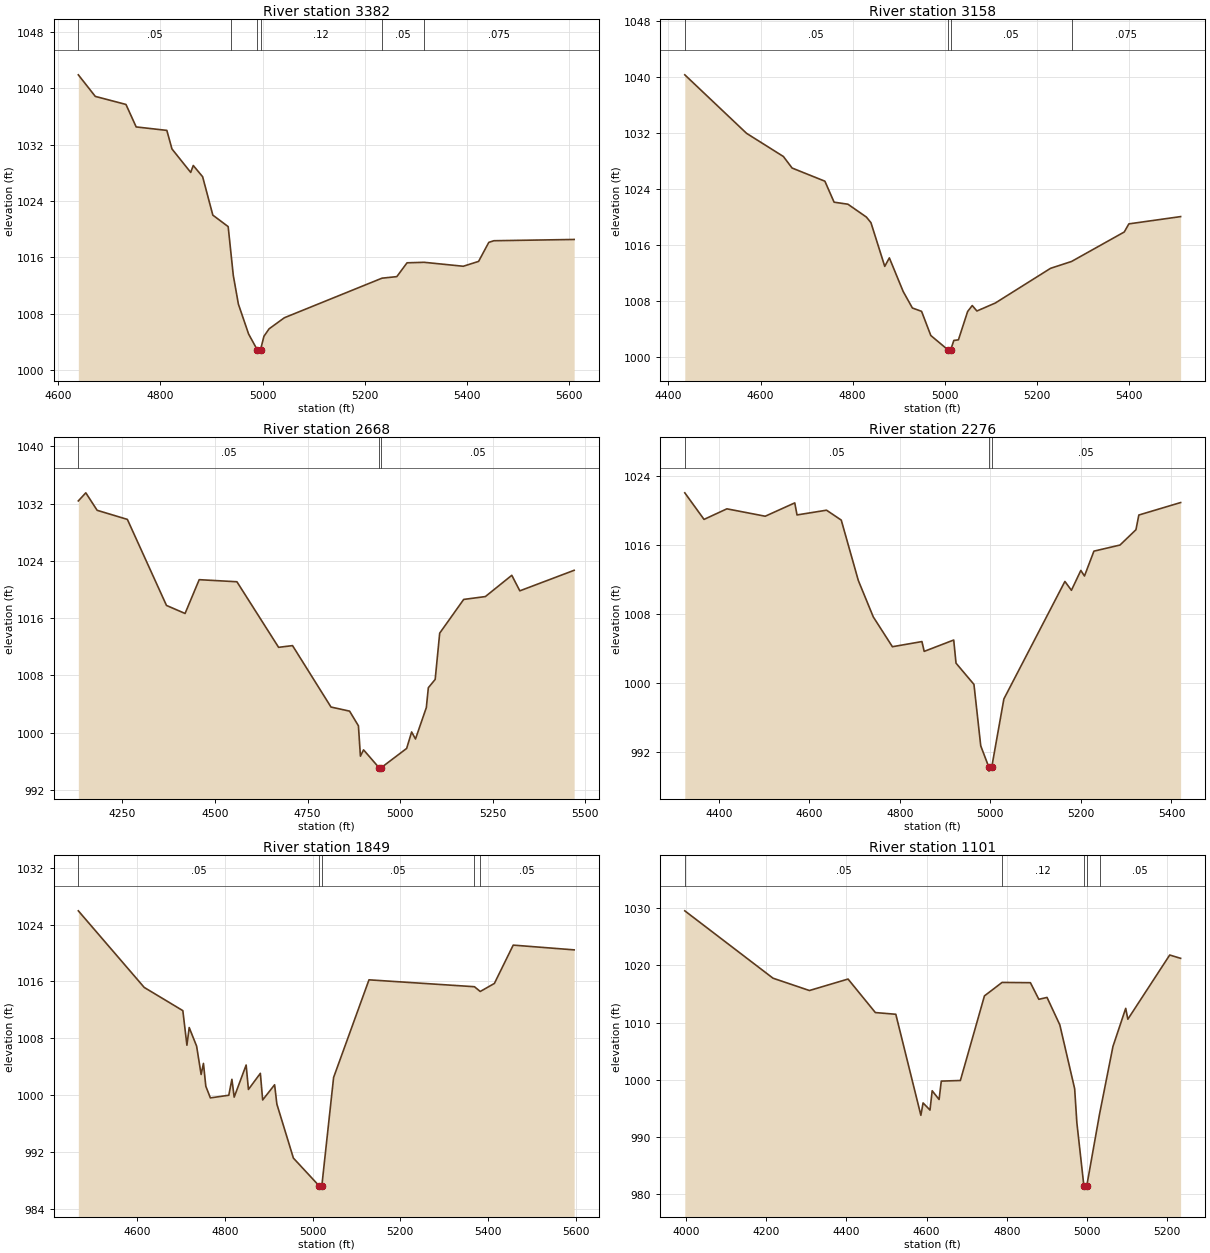
Type RM Length L Ch R = 1 ,3382    ,224,224,224
BEGIN DESCRIPTION:
Mapping XS 46642b27
END DESCRIPTION:
XS GIS Cut Line= 2
       2819078.9     10242840.09      2818108.74     10242831.43
#Sta/Elev= 30
  4639.6  1041.9  4672.8 1038.84  4732.8  1037.7  4752.8 1034.51  4812.8 1034.02
  4822.8 1031.39  4859.5 1028.06  4864.5 1029.04  4882.8 1027.45  4902.8    1022
  4932.8 1020.37  4937.6 1017.05  4942.8 1013.46  4952.8 1009.38  4972.8 1005.14
  4989.5 1002.93    4990 1002.43  4996.2 1002.93  5002.8 1004.82  5012.8 1005.87
  5042.8 1007.45  5233.8 1013.06  5262.8 1013.28  5282.8 1015.24  5316.3 1015.31
  5392.8 1014.75  5422.8 1015.44  5442.8 1018.14  5452.8 1018.37  5609.8 1018.55
#Mann= 6 ,-1 , 0
  4639.6     .05       0  4937.6     .12       0  4989.5     .07       0
  4996.2     .12       0  5233.8     .05       0  5316.3    .075       0
Bank Sta=4989.5,4996.2
XS Rating Curve= 0 ,0
Exp/Cntr=0.3,0.1

Type RM Length L Ch R = 1 ,3158    ,490,490,490
BEGIN DESCRIPTION:
Mapping XS a65733b9
END DESCRIPTION:
XS GIS Cut Line= 2
      2819139.75     10242683.84      2818063.37      10242657.8
#Sta/Elev= 30
  4435.5 1040.35  4569.6 1031.99  4649.6 1028.68  4668.5 1027.03  4739.7 1025.15
  4759.7 1022.15  4789.7 1021.86  4829.7 1020.03  4839.7 1019.23  4869.7 1012.98
  4879.7 1014.19  4909.7 1009.39  4929.7 1007.03  4949.7 1006.55  4969.7  1003.1
  5006.4 1001.08  5006.9 1000.58  5012.6 1000.58  5013.1 1001.08  5019.7 1002.39
  5029.7 1002.48  5049.7 1006.53  5059.7 1007.38  5069.8  1006.6  5109.8 1007.74
  5229.8  1012.7  5275.4 1013.68  5389.8 1017.89  5399.8 1019.05  5512.2 1020.09
#Mann= 4 ,-1 , 0
  4435.5     .05       0  5006.4     .03       0  5013.1     .05       0
  5275.4    .075       0
Bank Sta=5006.4,5013.1
XS Rating Curve= 0 ,0
Exp/Cntr=0.3,0.1

Type RM Length L Ch R = 1 ,2668    ,392,392,392
BEGIN DESCRIPTION:
Mapping XS e45433fa
END DESCRIPTION:
XS GIS Cut Line= 3
      2819365.42     10242536.27        2818697.     10242397.38
      2818090.02     10242145.92
#Sta/Elev= 30
  4130.8 1032.37    4151  1033.5  4181.6 1031.06  4263.3 1029.79    4369 1017.77
  4419.2 1016.65  4457.4 1021.37  4559.3 1021.08  4671.9 1011.92  4709.6 1012.16
  4813.5 1003.58  4863.7 1003.01  4887.6 1000.96    4893  996.72  4901.5   997.6
  4942.9  995.13  4943.4  994.63  4949.6  995.13  5017.9   997.8  5031.4  1000.1
  5041.8  999.12  5071.1 1003.51  5076.5 1006.28    5095 1007.44  5107.2  1013.9
    5172 1018.61  5230.6 1019.01    5302 1021.98  5323.7 1019.81  5470.5 1022.68
#Mann= 3 ,-1 , 0
  4130.8     .05       0  4942.9     .05       0  4949.6     .05       0
Bank Sta=4942.9,4949.6
XS Rating Curve= 0 ,0
Exp/Cntr=0.3,0.1

Type RM Length L Ch R = 1 ,2276    ,427,427,427
BEGIN DESCRIPTION:
Mapping XS ffbb0663
END DESCRIPTION:
XS GIS Cut Line= 4
      2819547.74     10242423.43      2818948.73     10242336.62
      2818861.93     10242206.41      2818601.55     10241998.11
#Sta/Elev= 30
    4325 1022.07  4367.5 1018.98    4418 1020.21  4502.7 1019.35  4567.9  1020.9
  4572.9  1019.5  4638.1 1020.05  4670.6  1018.9  4708.3 1011.88  4741.4 1007.64
  4783.6 1004.18  4848.8 1004.78  4853.8 1003.64    4919 1004.96  4924.1 1002.27
  4963.7   999.8  4978.7  992.66  4996.3  990.22  4996.8  989.72  5003.1  990.22
  5029.8  998.11  5164.6 1011.77    5179 1010.74  5199.8 1013.05  5207.8  1012.4
  5228.7 1015.29  5286.3    1016  5321.5 1017.78  5327.9 1019.49  5420.2 1020.94
#Mann= 3 ,-1 , 0
    4325     .05       0  4996.3     .05       0  5003.1     .05       0
Bank Sta=4996.3,5003.1
XS Rating Curve= 0 ,0
Exp/Cntr=0.3,0.1

Type RM Length L Ch R = 1 ,1849    ,748,748,748
BEGIN DESCRIPTION:
Mapping XS 195d6796
END DESCRIPTION:
XS GIS Cut Line= 6
      2819773.18      10242263.3      2819262.76     10242103.58
       2819082.2     10242079.27      2819002.34     10242096.63
      2818880.81      10242075.8      2818686.32     10241999.39
#Sta/Elev= 30
  4465.6 1025.93  4615.9 1015.14    4704 1011.87  4713.3    1007  4718.5 1009.49
  4735.4 1006.87  4745.7 1002.88    4751 1004.44  4756.4 1001.22  4766.8  999.58
  4808.8  999.95  4815.9  1002.2  4821.1  999.69  4848.4 1004.21  4853.6 1000.77
  4880.8 1003.04  4886.1  999.29  4913.3 1001.43  4918.5   998.7  4956.2   991.1
  5014.3  987.23  5014.8  986.73  5021.1  987.23  5047.9 1002.46  5128.6 1016.21
  5369.1 1015.24  5382.4 1014.57  5414.6  1015.7  5457.6  1021.1  5596.6 1020.43
#Mann= 5 ,-1 , 0
  4465.6     .05       0  5014.3     .05       0  5021.1     .05       0
  5369.1     .12       0  5382.4     .05       0
Bank Sta=5014.3,5021.1
XS Rating Curve= 0 ,0
Exp/Cntr=0.3,0.1

Type RM Length L Ch R = 1 ,1101    ,207,207,207
BEGIN DESCRIPTION:
Mapping XS 51eff019
END DESCRIPTION:
XS GIS Cut Line= 4
      2819818.33     10242093.16      2819221.09     10241808.44
      2819113.45     10241804.96      2818669.85     10241950.52
#Sta/Elev= 30
  3997.3 1029.57  4217.2 1017.77    4308 1015.61  4404.3 1017.62  4472.4 1011.75
  4523.4 1011.45  4585.9  993.75  4591.4  995.92  4608.6  994.67  4614.1  998.05
  4631.3  996.52  4636.8  999.74  4684.4  999.85  4744.4 1014.67  4788.4 1017.03
    4859 1016.98    4880 1014.07  4900.4  1014.4  4932.3  1009.6  4969.3  998.41
  4974.8  992.45  4992.4  981.32  4992.9  980.82  4999.3  981.32  5031.3  993.94
  5064.8 1005.81  5096.6 1012.49  5101.9 1010.58  5206.3 1021.83  5233.5 1021.25
#Mann= 5 ,-1 , 0
  3997.3     .05       0  4788.4     .12       0  4992.4     .07       0
  4999.3     .12       0  5031.3     .05       0
Bank Sta=4992.4,4999.3
XS Rating Curve= 0 ,0
Exp/Cntr=0.3,0.1