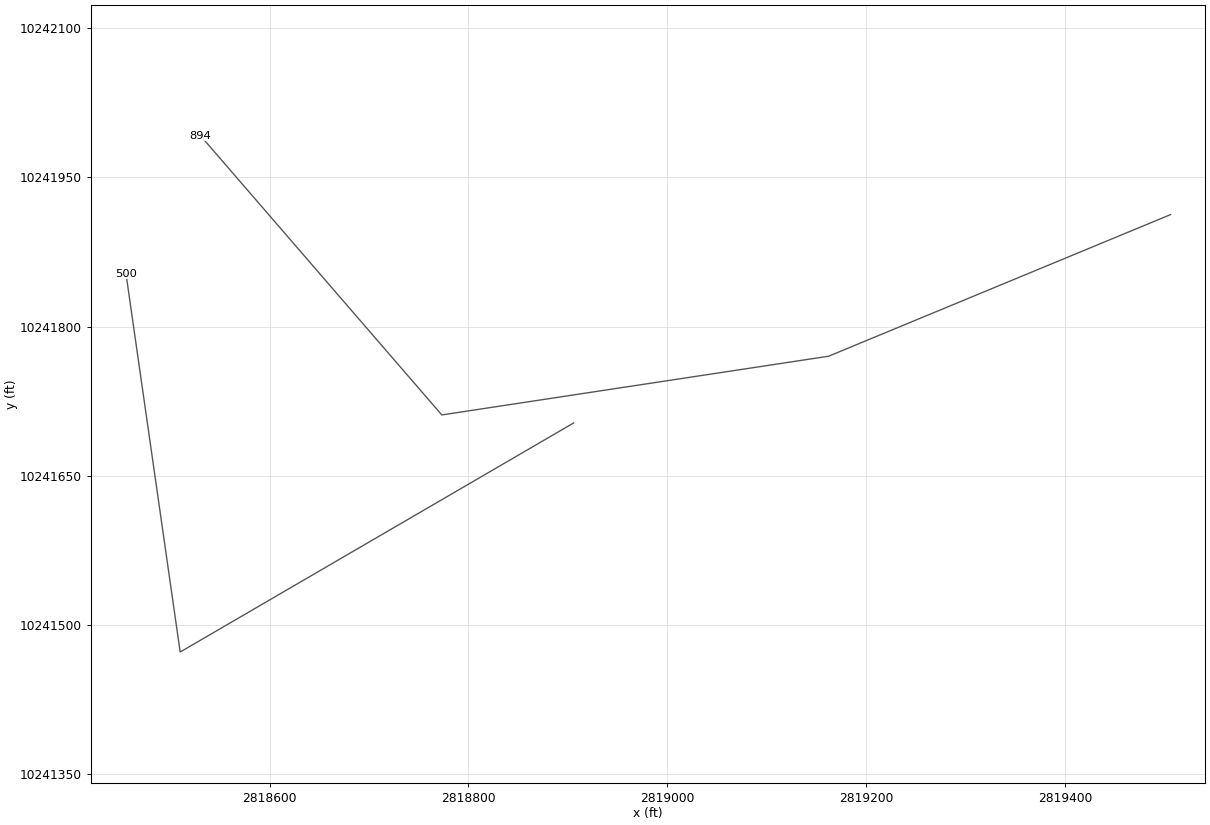
HEC-RAS study BUTTERY CREEK.prj: BUTTERY CREEK Base Level Engineering

--- BUTTERY CREEK.g01 (geometry) --- (continued)

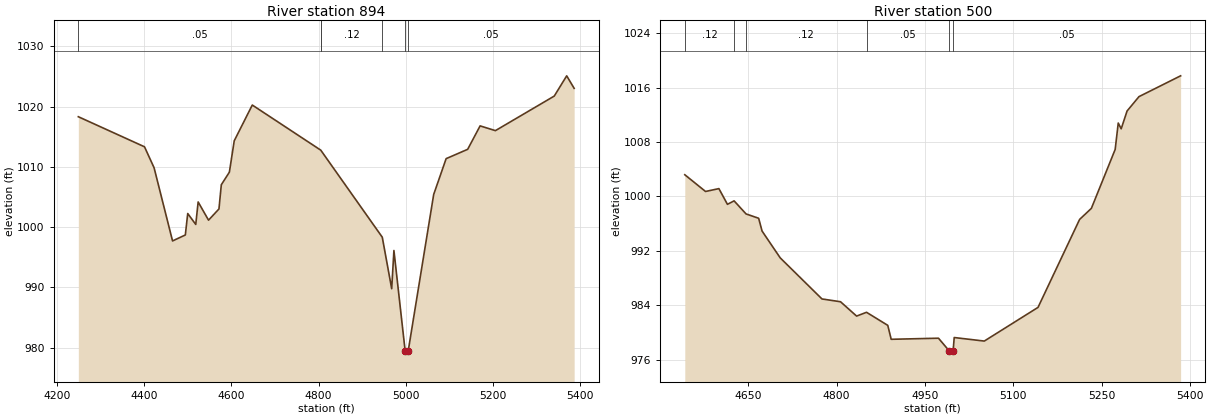
Type RM Length L Ch R = 1 ,894     ,394,394,394
BEGIN DESCRIPTION:
Mapping XS 9a6edd03
END DESCRIPTION:
XS GIS Cut Line= 4
      2819505.85     10241912.62      2819162.06     10241770.24
      2818773.17     10241711.21      2818530.42     10241992.11
#Sta/Elev= 30
  4249.2 1018.32  4400.9 1013.33  4422.9 1009.84  4465.2   997.7  4494.5  998.69
    4500 1002.25  4518.4 1000.44  4523.9 1004.17  4547.7 1001.15  4571.6 1003.01
    4577 1007.03  4595.5 1009.12  4606.6 1014.32    4648 1020.26  4804.8 1012.78
    4805 1012.77    4946  998.32  4967.6  989.77  4972.7  996.11  4998.5  979.41
    4999  978.91  5005.4  979.41  5063.9 1005.42  5092.4 1011.36  5141.8 1012.91
  5170.3  1016.8  5205.4 1016.01  5340.3 1021.75  5368.8 1025.11  5385.9 1023.03
#Mann= 6 ,-1 , 0
  4249.2     .05       0  4804.8     .05       0    4805     .12       0
    4946     .05       0  4998.5     .05       0  5005.4     .05       0
Bank Sta=4998.5,5005.4
XS Rating Curve= 0 ,0
Exp/Cntr=0.3,0.1

Type RM Length L Ch R = 1 ,500     ,0,0,0
BEGIN DESCRIPTION:
BUTTERY CREEK 1.0
END DESCRIPTION:
XS GIS Cut Line= 3
      2818905.71     10241703.13      2818510.15     10241472.86
      2818455.69     10241853.08
#Sta/Elev= 30
  4542.3 1003.18  4577.5 1000.72  4600.2 1001.14  4614.7  998.83    4626  999.34
  4646.3  997.42  4667.7  996.78  4673.5   994.9  4704.3  990.96  4775.2  984.92
  4806.7  984.51    4834   982.4  4850.8  982.96  4886.9  981.04  4892.7  978.99
    4973  979.15    4991  977.31  4991.5  976.81  4997.9  977.31  4999.7  979.25
  5050.8  978.73    5142  983.68  5212.6  996.61  5232.6  998.24    5273  1006.9
  5278.2 1010.78  5283.2 1009.93  5293.2 1012.55  5313.4 1014.66  5384.1 1017.72
#Mann= 6 ,-1 , 0
  4542.3     .12       0    4626     .05       0  4646.3     .12       0
  4850.8     .05       0    4991     .05       0  4997.9     .05       0
Bank Sta=4991,4997.9
XS Rating Curve= 0 ,0
Exp/Cntr=0.3,0.1

Chan Stop Cuts=-1
Use User Specified Reach Order=0
Composite Channel Slope=5