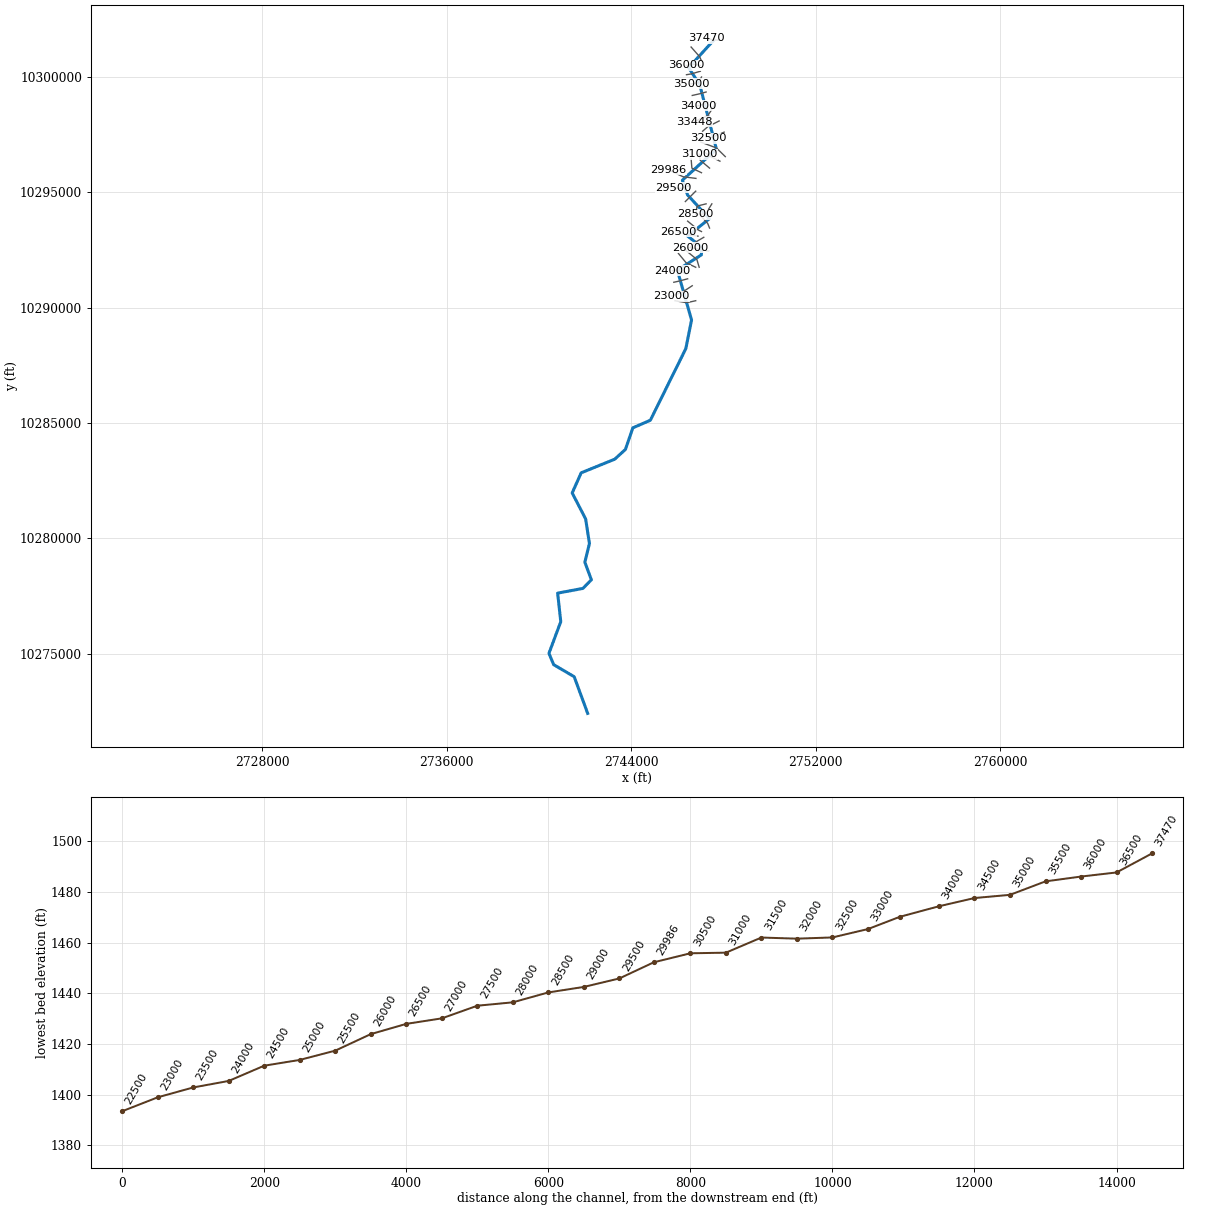
--- COLD CREEK.prj (project) ---

Proj Title=COLD CREEK Base Level Engineering
Current Plan=p01
Default Exp/Contr=0.3,0.1
English Units
Geom File=g01
Flow File=f01
Plan File=p01
Y Axis Title=Elevation
X Axis Title(PF)=Main Channel Distance
X Axis Title(XS)=Station
BEGIN DESCRIPTION:
COLD CREEK
END DESCRIPTION:
DSS Export Rating Curves= 0
DSS Export Rating Curve Sorted= 0
DSS Export Volume Flow Curves= 0
DXF OffsetX= 0
DXF OffsetY= 0
DXF ScaleX= 1
DXF ScaleY= 10

--- COLD CREEK.p01 (plan) ---

Plan Title=Multiple Run
Short Identifier=Multiple
Geom File=g01
Flow File=f01
Subcritical Flow
K Sum by GR= 0
Std Step Tol= 0.01
Critical Tol= 0.01
Num of Std Step Trials= 20
Max Error Tol= 0.3
Flow Tol Ratio= 0.001
Split Flow NTrial= 30
Split Flow Tol= 0.02
Split Flow Ratio= 0.02
Log Output Level= 0
Friction Slope Method= 1
Unsteady Friction Slope Method= 2
Unsteady Bridges Friction Slope Method= 1
Parabolic Critical Depth
Global Vel Dist=  1 , 1 , 1
Global Log Level= 0
CheckData=True
Encroach Param= -1, 0, 0, 0
BEGIN DESCRIPTION:
Multiple Run
END DESCRIPTION:

--- COLD CREEK.f01 (steady flow) ---

Flow Title=Multiple
Program Version=4.10
Number of Profiles= 7
Profile Names=10-year,25-year,50-year,1pct_min,100-year,1pct_plu,500-year
River Rch & RM=COLD CREEK,Reach-1         ,37470
    2160    3877    7717    6089   11224   20689   15691
River Rch & RM=COLD CREEK,Reach-1         ,36000
    2984    5513   10299    7760   14997   28983   20716
River Rch & RM=COLD CREEK,Reach-1         ,30500
    3391    6318   11598    9877   16895   28899   23247
River Rch & RM=COLD CREEK,Reach-1         ,27500
    3793    7120   12872   10743   18793   32875   25851
River Rch & RM=COLD CREEK,Reach-1         ,20500
    4048    7634   13631   11692   19930   33972   27418
River Rch & RM=COLD CREEK,Reach-1         ,13500
    4974    9448   16604   16689   24251   35240   33107
River Rch & RM=COLD CREEK,Reach-1         ,9500
    5425   10321   18015   13911   26279   49646   35742
River Rch & RM=COLD CREEK,Reach-1         ,9000
    5428   10336   17984   16509   26247   41728   35715
River Rch & RM=COLD CREEK,Reach-1         ,5500
    6196   11809   20361   15917   29648   55226   40115
Boundary for River Rch & Prof#=COLD CREEK,Reach-1         , 1
Up Type= 0
Dn Type= 3
Dn Slope=0.001
Boundary for River Rch & Prof#=COLD CREEK,Reach-1         , 2
Up Type= 0
Dn Type= 3
Dn Slope=0.001
Boundary for River Rch & Prof#=COLD CREEK,Reach-1         , 3
Up Type= 0
Dn Type= 3
Dn Slope=0.001
Boundary for River Rch & Prof#=COLD CREEK,Reach-1         , 4
Up Type= 0
Dn Type= 3
Dn Slope=0.001
Boundary for River Rch & Prof#=COLD CREEK,Reach-1         , 5
Up Type= 0
Dn Type= 3
Dn Slope=0.001
Boundary for River Rch & Prof#=COLD CREEK,Reach-1         , 6
Up Type= 0
Dn Type= 3
Dn Slope=0.001
Boundary for River Rch & Prof#=COLD CREEK,Reach-1         , 7
Up Type= 0
Dn Type= 3
Dn Slope=0.001
DSS Import GetInterval= 0
DSS Import GetPeak= 0
DSS Import FillOption= 0

--- COLD CREEK.g01 (geometry) ---

Geom Title=Existing Conditions
Program Version=4.10

River Reach=COLD CREEK      ,Reach-1
Reach XY= 30
      2747600.75       10301613.       2746497.5       10300408.
      2746979.25       10299671.      2747703.75       10296874.
      2746226.75       10295526.       2746452.5       10294889.
      2747399.25       10293861.      2746456.25       10293105.
       2747079.5       10292617.      2747046.25       10292287.
      2746008.75       10291627.      2746625.25       10289467.
       2746377.5       10288227.        2744840.       10285121.
       2744079.5       10284790.      2743758.75       10283856.
        2743294.       10283431.      2741839.25       10282841.
       2741449.5       10281968.      2742032.75       10280841.
       2742197.5       10279777.      2741999.25       10278964.
      2742281.75       10278202.      2741913.25       10277828.
      2740819.25       10277624.      2740954.25       10276384.
        2740442.       10275014.        2740648.       10274521.
        2741536.       10274000.       2742121.5       10272410.

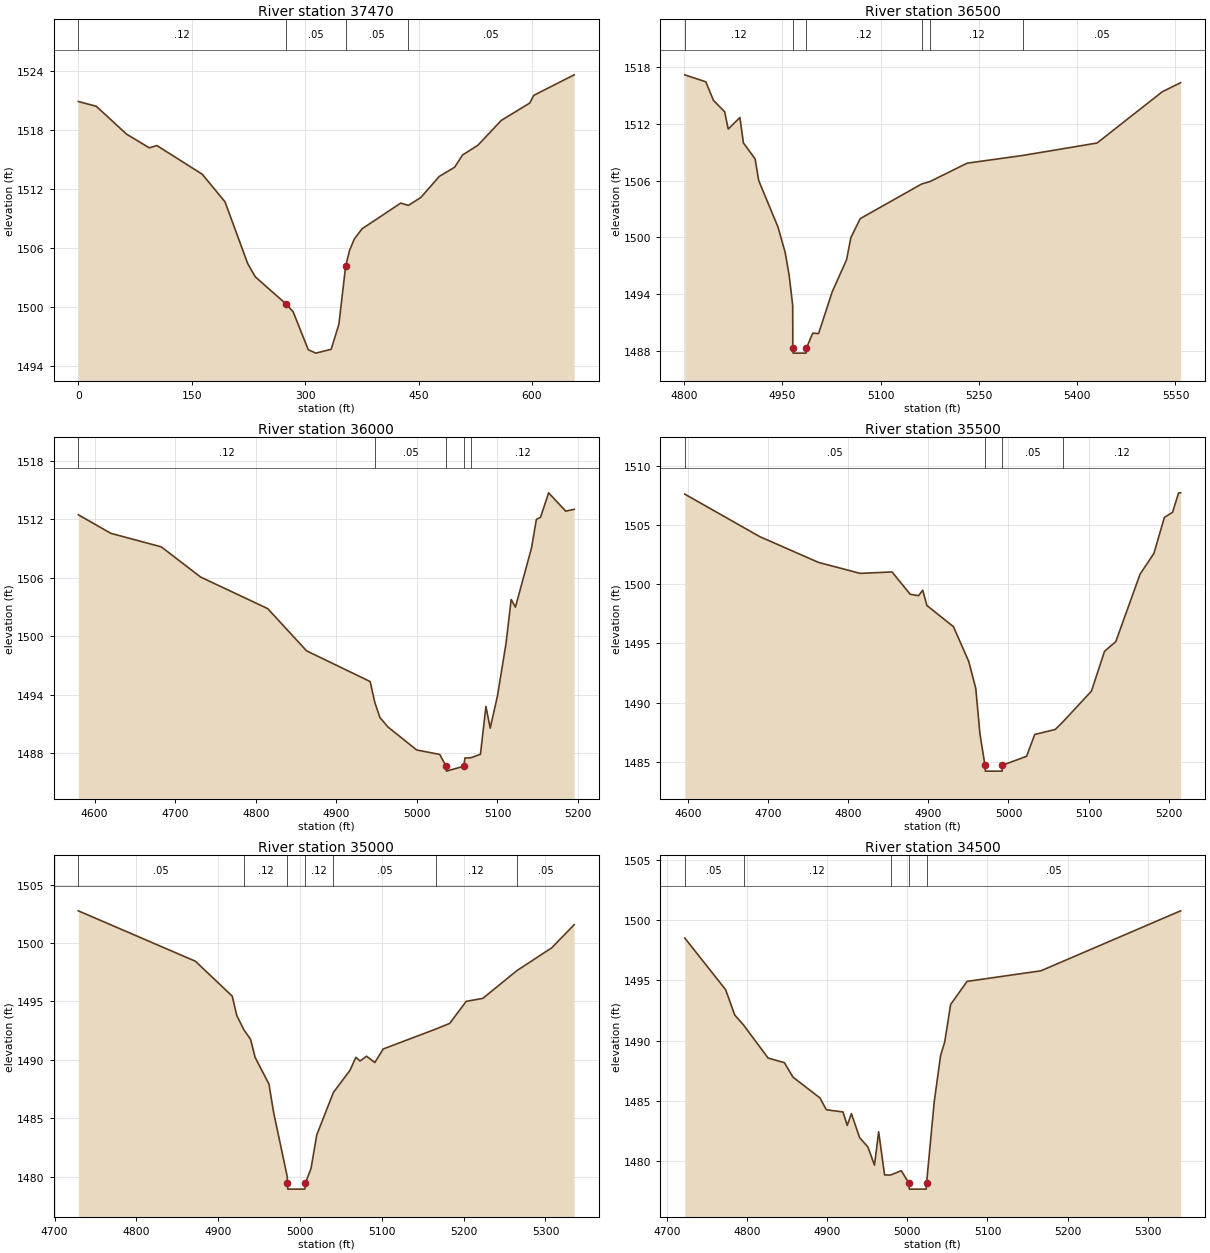
Type RM Length L Ch R = 1 ,37470   ,500,500,500
BEGIN DESCRIPTION:
COLD CREEK 74.0
END DESCRIPTION:
XS GIS Cut Line= 3
      2747909.47     10301595.78      2747589.23     10301610.49
       2747261.2     10301679.81
#Sta/Elev= 30
       0 1520.86    23.8 1520.37    63.8 1517.54    93.9 1516.15   103.9 1516.38
     164 1513.46     194 1510.66     224 1504.39     234 1503.04   274.1 1500.32
   284.1 1499.49   304.1 1495.63   314.1 1495.28   334.4 1495.67   344.6  1498.2
   353.6 1504.14   358.7 1505.72   365.1 1506.89   375.3 1507.92   426.4 1510.53
   436.6  1510.3   453.1 1511.11   477.5 1513.25   497.7 1514.18   508.2 1515.42
   528.6 1516.42   559.3 1518.93   597.2 1520.71   602.3 1521.48   655.8 1523.57
#Mann= 4 ,-1 , 0
       0     .12       0   274.1     .05       0   353.6     .05       0
   436.6     .05       0
Bank Sta=274.1,353.6
XS Rating Curve= 0 ,0
Exp/Cntr=0.3,0.1

Type RM Length L Ch R = 1 ,36500   ,500,500,500
BEGIN DESCRIPTION:
COLD CREEK 73.0
END DESCRIPTION:
XS GIS Cut Line= 3
      2747055.69      10300703.1      2746974.76     10300884.79
      2746605.66     10301303.14
#Sta/Elev= 30
  4801.1 1517.18  4833.2 1516.44  4844.9 1514.47  4861.9 1513.28  4867.4 1511.45
  4885.2 1512.67  4890.6 1509.98  4908.4  1508.3  4913.9 1506.01  4943.4 1501.08
  4954.4 1498.38  4960.4 1495.97  4965.8 1492.82    4966 1488.26  4966.5 1487.76
  4986.1 1487.76  4986.6 1488.26  4996.3 1489.87  5005.3 1489.83  5026.2 1494.26
    5048 1497.63  5054.6 1499.98  5068.9 1501.98  5162.4 1505.63  5175.4  1505.9
    5232 1507.84  5317.1 1508.66  5430.3 1509.97  5529.9 1515.39  5557.9 1516.35
#Mann= 6 ,-1 , 0
  4801.1     .12       0    4966     .07       0  4986.6     .12       0
  5162.4     .05       0  5175.4     .12       0  5317.1     .05       0
Bank Sta=4966,4986.6
XS Rating Curve= 0 ,0
Exp/Cntr=0.3,0.1

Type RM Length L Ch R = 1 ,36000   ,500,500,500
BEGIN DESCRIPTION:
COLD CREEK 72.0
END DESCRIPTION:
XS GIS Cut Line= 3
      2747005.71     10300503.11      2746590.31      10300566.4
      2746405.65      10300503.1
#Sta/Elev= 30
  4579.8 1512.44  4620.3 1510.53  4682.7 1509.15  4731.6 1506.05  4814.9 1502.81
  4863.1 1498.48    4942 1495.33  4947.8 1493.19  4954.1 1491.64  4964.2 1490.66
  4999.8 1488.31  5028.4 1487.85  5036.2 1486.64  5036.7 1486.14  5058.1 1486.64
  5059.7 1487.49    5067 1487.51  5078.9 1487.87  5085.7 1492.78    5091 1490.55
    5100 1493.85  5110.6 1499.22    5117 1503.75  5122.3 1502.96  5142.3 1509.05
  5148.3 1511.96  5153.5 1512.19  5163.5 1514.69  5184.8 1512.81  5195.2    1513
#Mann= 5 ,-1 , 0
  4579.8     .12       0  4947.8     .05       0  5036.2     .05       0
  5058.1     .05       0    5067     .12       0
Bank Sta=5036.2,5058.1
XS Rating Curve= 0 ,0
Exp/Cntr=0.3,0.1

Type RM Length L Ch R = 1 ,35500   ,500,500,500
BEGIN DESCRIPTION:
COLD CREEK 71.0
END DESCRIPTION:
XS GIS Cut Line= 3
      2747005.64      10300253.1      2746618.02     10300137.48
      2746405.68     10300103.11
#Sta/Elev= 30
  4595.5 1507.59  4689.4    1504  4762.4 1501.84  4814.6 1500.91  4854.5 1501.03
  4877.2 1499.15  4887.6 1499.03  4892.8 1499.49  4898.1  1498.2  4931.2 1496.42
  4950.3 1493.49  4959.1 1491.22  4964.4 1487.34  4970.6 1484.74  4971.1 1484.24
    4992 1484.24  4992.5 1484.74  5022.6 1485.49  5032.8 1487.33  5058.4 1487.75
  5068.1  1488.4  5103.7 1490.99    5120 1494.34  5134.1 1495.16  5164.4 1500.84
  5181.7 1502.59  5194.8 1505.63    5205 1506.06  5212.6  1507.7  5215.1  1507.7
#Mann= 4 ,-1 , 0
  4595.5     .05       0  4970.6     .05       0  4992.5     .05       0
  5068.1     .12       0
Bank Sta=4970.6,4992.5
XS Rating Curve= 0 ,0
Exp/Cntr=0.3,0.1

Type RM Length L Ch R = 1 ,35000   ,500,500,500
BEGIN DESCRIPTION:
COLD CREEK 70.0
END DESCRIPTION:
XS GIS Cut Line= 3
      2747055.66     10300003.07       2746935.9     10299760.08
      2746605.68     10299703.11
#Sta/Elev= 30
  4729.1 1502.77  4872.2 1498.45  4917.2 1495.46  4922.7 1493.81  4931.3 1492.59
  4939.6 1491.76  4945.2 1490.21  4962.1 1487.92  4967.7 1485.52  4984.5 1479.97
  4984.6 1479.42  4985.1 1478.92    5006 1478.92  5006.5 1479.42  5013.5 1480.69
  5020.5 1483.57  5040.9 1487.21  5061.1  1489.1  5068.3 1490.22  5073.4  1489.9
  5081.4 1490.31  5091.5 1489.77  5101.7 1490.93  5165.7 1492.63  5182.9 1493.12
  5203.2 1495.01  5223.5 1495.27  5265.2 1497.65  5307.7  1499.6  5335.1 1501.58
#Mann= 7 ,-1 , 0
  4729.1     .05       0  4931.3     .12       0  4984.6     .07       0
  5006.5     .12       0  5040.9     .05       0  5165.7     .12       0
  5265.2     .05       0
Bank Sta=4984.6,5006.5
XS Rating Curve= 0 ,0
Exp/Cntr=0.3,0.1

Type RM Length L Ch R = 1 ,34500   ,500,500,500
BEGIN DESCRIPTION:
COLD CREEK 69.0
END DESCRIPTION:
XS GIS Cut Line= 3
      2747255.67     10299353.11      2746988.37     10299277.81
      2746655.66     10299203.11
#Sta/Elev= 30
  4722.3 1498.51  4773.3 1494.22  4784.6 1492.12  4795.6 1491.29  4826.2 1488.55
  4846.6 1488.16  4857.3 1486.96    4891 1485.23  4898.9 1484.25  4919.7 1484.07
    4925 1482.95  4930.2 1483.93  4940.5 1481.93  4950.8 1481.16    4959 1479.65
  4964.2 1482.42  4971.6 1478.84  4979.1 1478.83  4992.4 1479.19    5002 1478.16
  5002.5 1477.66  5023.5 1477.66    5024 1478.16  5033.5 1484.89  5041.5 1488.76
  5046.6 1489.87    5054 1492.99  5074.5 1494.91  5166.7 1495.79    5341 1500.77
#Mann= 5 ,-1 , 0
  4722.3     .05       0  4795.6     .12       0  4979.1     .05       0
    5002     .05       0    5024     .05       0
Bank Sta=5002,5024
XS Rating Curve= 0 ,0
Exp/Cntr=0.3,0.1

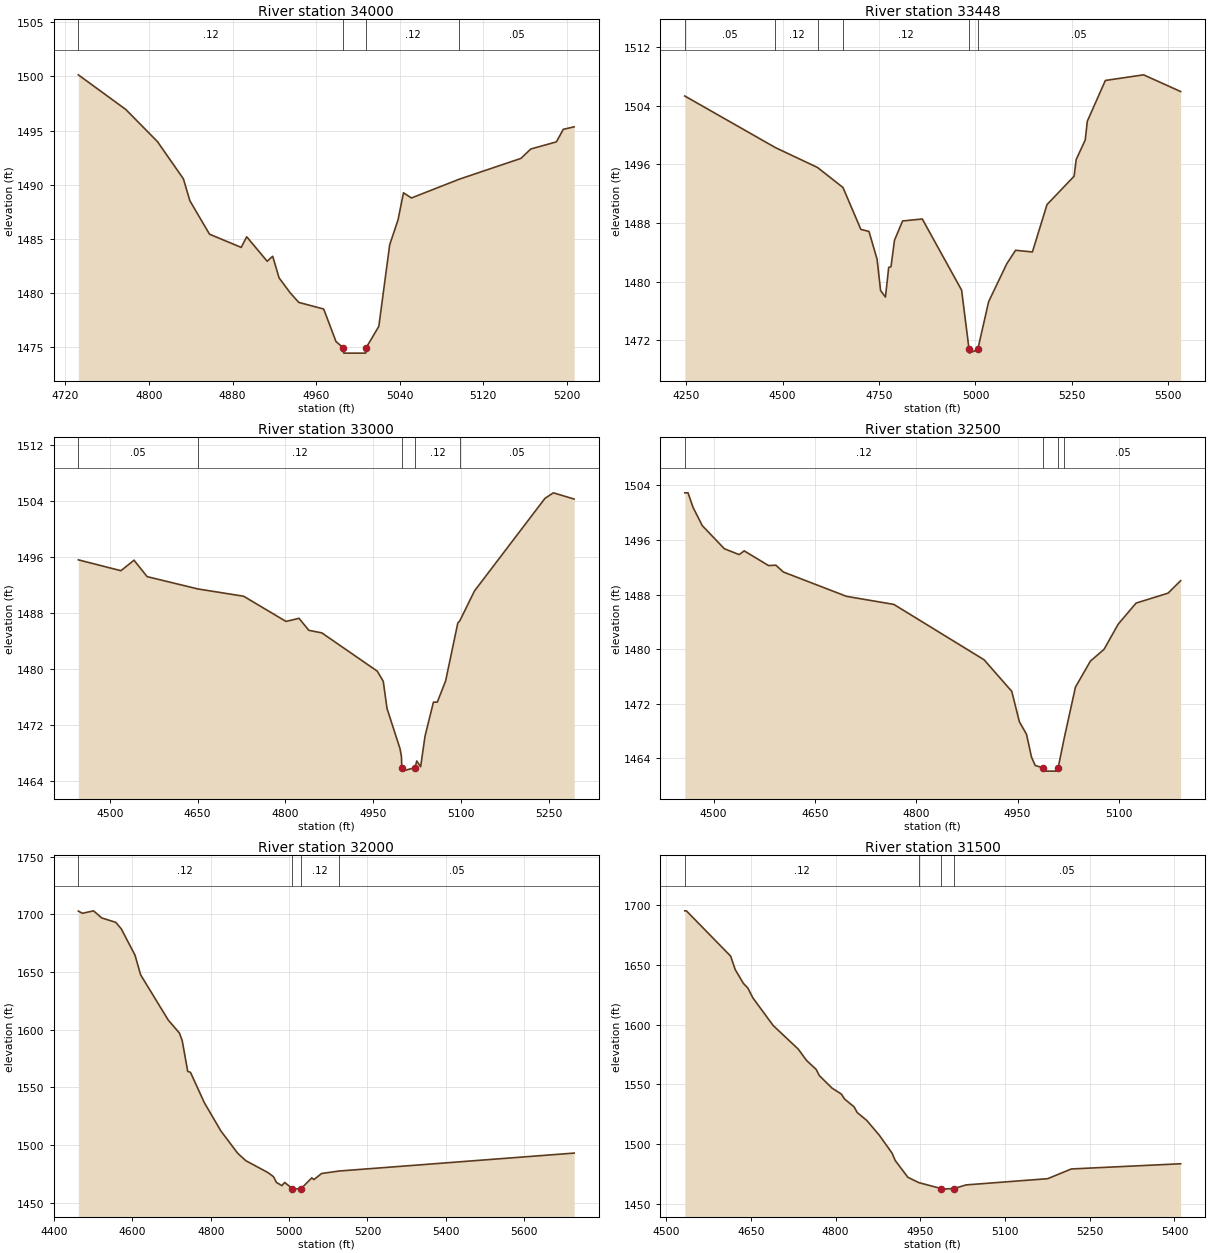
Type RM Length L Ch R = 1 ,34000   ,552,552,552
BEGIN DESCRIPTION:
COLD CREEK 68.0
END DESCRIPTION:
XS GIS Cut Line= 3
      2747355.67     10298903.11      2747104.96     10298809.27
      2746905.72     10298753.12
#Sta/Elev= 30
  4732.3 1500.15  4777.7 1496.95    4808 1493.98  4832.9 1490.53  4839.1  1488.5
  4857.9 1485.41  4888.2 1484.19  4893.5 1485.17  4913.1 1482.91  4918.4 1483.37
  4924.5 1481.37  4935.2 1479.98  4943.4  1479.1  4967.2 1478.49    4979 1475.48
  4985.9 1474.91  4986.4 1474.41  5007.4 1474.41  5007.9 1474.91    5020 1476.89
  5030.4 1484.43  5038.4 1486.74  5043.6 1489.24  5051.2 1488.76  5097.1  1490.5
    5156 1492.42  5165.5 1493.29    5190 1493.95  5196.6 1495.11    5207 1495.34
#Mann= 4 ,-1 , 0
  4732.3     .12       0  4985.9     .07       0  5007.9     .12       0
  5097.1     .05       0
Bank Sta=4985.9,5007.9
XS Rating Curve= 0 ,0
Exp/Cntr=0.3,0.1

Type RM Length L Ch R = 1 ,33448   ,448,448,448
BEGIN DESCRIPTION:
Mapping XS ab8add9f
END DESCRIPTION:
XS GIS Cut Line= 3
      2747685.18     10298865.83      2747323.06     10298322.64
       2746743.7     10298069.18
#Sta/Elev= 30
  4246.5 1505.34  4481.2  1498.3  4590.6 1495.58  4656.5 1492.85  4702.9 1487.13
  4723.9 1486.85  4744.9 1483.06    4754 1478.79  4766.6 1477.89    4775 1481.93
    4781 1482.04    4790 1485.64    4811 1488.28  4862.1 1488.55    4964 1478.84
  4983.4 1470.74  4983.9 1470.24  5005.9 1470.74  5034.1 1477.27  5080.9 1482.42
  5103.8 1484.28  5147.5 1484.05  5185.4 1490.52  5255.6 1494.39    5261 1496.67
  5284.4 1499.33  5289.9  1501.9  5336.6 1507.46  5435.7 1508.23  5531.7 1505.95
#Mann= 6 ,-1 , 0
  4246.5     .05       0  4481.2     .12       0  4590.6     .05       0
  4656.5     .12       0  4983.4     .05       0  5005.9     .05       0
Bank Sta=4983.4,5005.9
XS Rating Curve= 0 ,0
Exp/Cntr=0.3,0.1

Type RM Length L Ch R = 1 ,33000   ,500,500,500
BEGIN DESCRIPTION:
COLD CREEK 66.0
END DESCRIPTION:
XS GIS Cut Line= 3
      2747820.65     10298096.69      2747326.41     10297846.62
      2747105.72     10297653.14
#Sta/Elev= 30
  4446.1 1495.61  4518.9 1494.06  4541.3 1495.56  4563.7 1493.21  4650.5 1491.45
  4728.6 1490.41    4801 1486.81  4823.3 1487.25    4840 1485.54  4862.3 1485.17
    4957  1479.7  4967.2 1478.26  4973.7 1474.36    4996 1468.59  4998.3  1467.5
    4999 1465.91  4999.5 1465.41  5021.6 1465.91  5024.5 1466.86  5031.1 1466.04
  5038.7 1470.44    5053 1475.27  5059.6 1475.27  5073.8  1478.3  5094.7  1486.6
  5097.9 1486.87  5123.2 1491.17  5243.7 1504.41    5258 1505.19  5293.5  1504.3
#Mann= 5 ,-1 , 0
  4446.1     .05       0  4650.5     .12       0    4999     .07       0
  5021.6     .12       0  5097.9     .05       0
Bank Sta=4999,5021.6
XS Rating Curve= 0 ,0
Exp/Cntr=0.3,0.1

Type RM Length L Ch R = 1 ,32500   ,500,500,500
BEGIN DESCRIPTION:
COLD CREEK 65.0
END DESCRIPTION:
XS GIS Cut Line= 3
      2748039.43     10297614.06      2747542.06     10297397.19
       2747355.7     10297353.11
#Sta/Elev= 30
  4457.4 1502.91  4462.2 1502.91  4469.6 1500.78  4483.3  1498.1    4516 1494.71
  4537.9 1493.85  4545.3  1494.4  4581.5 1492.24  4592.2  1492.3  4603.3  1491.3
  4696.8 1487.73  4766.9 1486.55  4900.5 1478.43  4941.5  1473.8  4952.8 1469.34
  4963.3 1467.51  4970.7 1464.16  4976.2 1462.93  4987.5  1462.6    4988  1462.1
  5009.7  1462.1  5010.2  1462.6  5019.3 1467.01  5035.8 1474.42  5057.9 1478.23
  5078.1 1479.96    5099 1483.64  5125.5 1486.74  5172.9  1488.2  5191.5 1490.03
#Mann= 4 ,-1 , 0
  4457.4     .12       0  4987.5     .07       0  5010.2     .12       0
  5019.3     .05       0
Bank Sta=4987.5,5010.2
XS Rating Curve= 0 ,0
Exp/Cntr=0.3,0.1

Type RM Length L Ch R = 1 ,32000   ,500,500,500
BEGIN DESCRIPTION:
COLD CREEK 64.0
END DESCRIPTION:
XS GIS Cut Line= 3
       2748088.2     10296550.77      2747703.75      10296927.4
       2747022.3     10297182.41
#Sta/Elev= 30
  4461.8 1702.94  4472.3    1701  4500.6 1703.16  4521.7 1696.98  4557.2 1693.21
  4571.3  1687.6  4606.6 1664.62  4620.8 1647.64  4691.5 1608.29  4719.8 1597.13
  4726.9 1590.69  4741.1 1563.81  4748.1 1562.98  4783.5 1536.63  4825.9 1512.03
  4868.4 1492.83  4889.5 1486.28  4946.1 1475.94  4960.2 1472.37  4967.4 1467.48
  4981.5 1464.65  4988.5 1467.46  5007.9 1462.12  5008.4 1461.62  5030.6 1462.12
  5057.9  1471.4  5063.2 1469.89  5082.8 1475.18  5127.4 1477.33  5727.6 1492.91
#Mann= 4 ,-1 , 0
  4461.8     .12       0  5007.9     .07       0  5030.6     .12       0
  5127.4     .05       0
Bank Sta=5007.9,5030.6
XS Rating Curve= 0 ,0
Exp/Cntr=0.3,0.1

Type RM Length L Ch R = 1 ,31500   ,500,500,500
BEGIN DESCRIPTION:
COLD CREEK 63.0
END DESCRIPTION:
XS GIS Cut Line= 3
      2747855.66     10296353.12      2747437.45      10296560.7
      2747105.67     10296803.12
#Sta/Elev= 30
  4533.1 1695.29  4535.9 1695.29  4614.3 1657.32  4622.4 1646.03  4636.7 1634.55
  4644.7 1630.63  4653.5 1622.44  4689.4 1599.28    4734 1579.39  4748.8 1569.81
  4765.6 1562.45  4771.2 1557.26  4793.6 1546.79  4810.4 1541.68    4816 1537.56
  4832.8 1531.02  4838.4 1526.24  4855.2 1519.67  4877.6 1507.16  4900.1  1492.2
  4905.6 1486.08    4928 1472.02  4947.3 1467.53  4986.8 1462.56  4987.3 1462.06
  5009.6 1462.56  5031.3 1465.61  5175.6 1470.81  5217.4 1478.96  5410.9 1483.32
#Mann= 4 ,-1 , 0
  4533.1     .12       0  4947.3     .05       0  4986.8     .05       0
  5009.6     .05       0
Bank Sta=4986.8,5009.6
XS Rating Curve= 0 ,0
Exp/Cntr=0.3,0.1

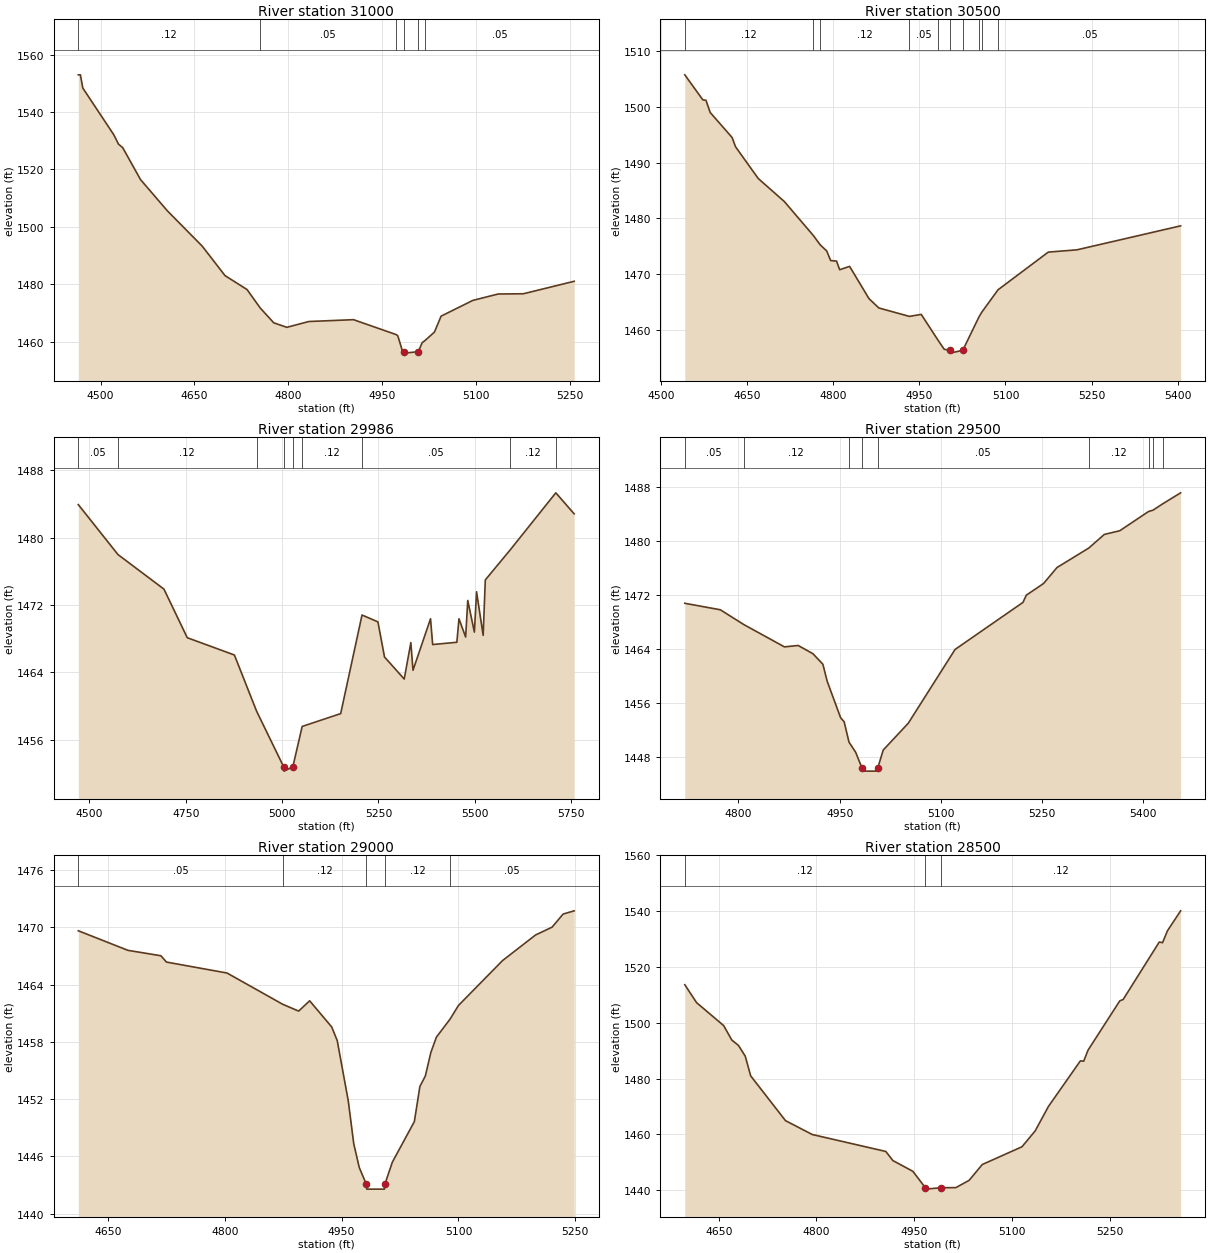
Type RM Length L Ch R = 1 ,31000   ,500,500,500
BEGIN DESCRIPTION:
COLD CREEK 62.0
END DESCRIPTION:
XS GIS Cut Line= 3
      2747405.72     10296053.09      2746996.84     10296399.04
      2746955.68     10296653.13
#Sta/Elev= 30
  4464.4 1552.93  4467.7 1552.93  4471.6 1548.31    4521 1532.12  4528.7 1528.79
  4535.3 1527.62  4563.9 1516.47  4606.7 1505.63  4662.7 1493.28    4699 1483.06
  4734.2 1478.22  4755.4 1471.78    4777 1466.63  4797.9 1465.07    4833 1467.09
  4904.5 1467.73    4973 1462.52  4975.3 1462.14  4982.5 1457.03  4985.4 1456.59
  4985.9 1456.09  5008.2 1456.59  5014.3 1459.73    5019 1460.49    5034 1463.43
  5044.6 1468.96  5095.3 1474.43  5135.8 1476.66  5176.3 1476.75  5257.4 1481.09
#Mann= 6 ,-1 , 0
  4464.4     .12       0  4755.4     .05       0    4973     .12       0
  4985.4     .07       0  5008.2     .12       0    5019     .05       0
Bank Sta=4985.4,5008.2
XS Rating Curve= 0 ,0
Exp/Cntr=0.3,0.1

Type RM Length L Ch R = 1 ,30500   ,514,514,514
BEGIN DESCRIPTION:
COLD CREEK 61.0
END DESCRIPTION:
XS GIS Cut Line= 3
       2747055.7      10295853.1      2746640.48      10296049.2
      2746605.68     10296453.11
#Sta/Elev= 30
  4540.8 1505.76  4572.2 1501.28  4577.7 1501.19  4585.1 1499.01  4623.3 1494.52
  4629.3 1492.85  4668.8 1487.17  4714.3 1483.04    4765 1476.93  4776.9 1475.27
  4788.2 1474.17  4795.2 1472.44  4805.4 1472.35  4810.9  1470.8  4828.2  1471.4
    4862 1465.61  4879.2 1463.94  4932.4 1462.43  4953.1 1462.79  4982.9 1458.08
  4993.1 1456.54  5002.4 1456.34  5002.9 1455.84  5025.5 1456.34  5053.6  1462.3
  5058.3 1463.13  5087.1 1467.21  5174.6 1473.96  5224.7 1474.37  5405.4 1478.67
#Mann= 10 ,-1 , 0
  4540.8     .12       0    4765     .05       0  4776.9     .12       0
  4932.4     .05       0  4982.9     .12       0  5002.4     .07       0
  5025.5     .12       0  5053.6     .05       0  5058.3     .12       0
  5087.1     .05       0
Bank Sta=5002.4,5025.5
XS Rating Curve= 0 ,0
Exp/Cntr=0.3,0.1

Type RM Length L Ch R = 1 ,29986   ,486,486,486
BEGIN DESCRIPTION:
Mapping XS 771cecd2
END DESCRIPTION:
XS GIS Cut Line= 3
      2746816.04     10295606.75       2746254.8     10295679.17
      2745603.01     10295986.96
#Sta/Elev= 30
  4471.2  1483.9  4574.1 1477.98  4693.4 1473.88  4753.9 1468.12  4876.2 1466.07
  4933.9  1459.4  5004.2  1452.8  5004.7  1452.3  5027.8  1452.8  5052.1  1457.6
    5152 1459.12  5207.4 1470.81  5248.6    1470  5265.8 1465.83  5316.9 1463.22
  5334.1 1467.54  5339.7 1464.26  5385.2 1470.37  5390.7 1467.31  5453.5 1467.58
    5459 1470.37  5476.3  1468.2  5481.8 1472.54    5499 1468.78  5504.6 1473.57
  5521.8  1468.4  5527.3 1474.97  5591.5 1478.51  5710.3  1485.3  5757.9 1482.81
#Mann= 9 ,-1 , 0
  4471.2     .05       0  4574.1     .12       0  4933.9     .05       0
  5004.2     .03       0  5027.8     .05       0  5052.1     .12       0
  5207.4     .05       0  5591.5     .12       0  5710.3     .05       0
Bank Sta=5004.2,5027.8
XS Rating Curve= 0 ,0
Exp/Cntr=0.3,0.1

Type RM Length L Ch R = 1 ,29500   ,500,500,500
BEGIN DESCRIPTION:
COLD CREEK 59.0
END DESCRIPTION:
XS GIS Cut Line= 4
      2746555.65      10295303.1      2746290.75     10295213.95
      2746161.62      10295171.5      2745843.01     10295194.88
#Sta/Elev= 30
  4720.5 1470.74  4773.2 1469.78  4807.8  1467.6  4868.2 1464.29  4888.5  1464.5
  4910.4 1463.28  4925.2 1461.72  4931.5 1459.22  4951.5  1453.8  4956.7 1453.21
  4963.9  1450.2  4973.7 1448.71    4983 1446.41  4983.5 1445.91  5006.1 1445.91
  5006.6 1446.41  5014.6 1449.03  5051.7 1452.99  5121.1 1463.91  5221.7 1470.87
  5226.7 1471.94  5252.2 1473.66  5272.2 1476.03  5319.1  1478.9  5342.4 1480.93
  5365.2 1481.47  5407.9 1484.32  5414.4 1484.51  5429.3 1485.48  5455.4 1487.08
#Mann= 9 ,-1 , 0
  4720.5     .05       0  4807.8     .12       0  4963.9     .05       0
    4983     .05       0  5006.6     .05       0  5319.1     .12       0
  5407.9     .05       0  5414.4     .12       0  5429.3     .05       0
Bank Sta=4983,5006.6
XS Rating Curve= 0 ,0
Exp/Cntr=0.3,0.1

Type RM Length L Ch R = 1 ,29000   ,500,500,500
BEGIN DESCRIPTION:
COLD CREEK 58.0
END DESCRIPTION:
XS GIS Cut Line= 3
      2746805.66     10295053.09      2746531.77     10294778.41
      2746355.66     10294603.09
#Sta/Elev= 30
  4612.1 1469.64  4675.7 1467.59  4718.1 1467.02  4725.2 1466.36    4803 1465.21
  4874.3 1461.94  4894.9 1461.22    4909  1462.3  4937.3 1459.56  4944.4 1458.13
  4958.6  1451.8  4965.6 1447.32  4972.7 1444.82  4981.8 1443.06  4982.3 1442.56
    5005 1442.56  5005.5 1443.06  5015.1 1445.38  5043.4 1449.64  5050.5 1453.32
  5057.5 1454.42  5064.6 1456.89  5071.7 1458.49  5089.4  1460.4    5100 1461.81
  5156.5 1466.51    5199  1469.2  5220.2 1470.02  5234.3 1471.39  5248.5 1471.73
#Mann= 5 ,-1 , 0
  4612.1     .05       0  4874.3     .12       0  4981.8     .07       0
  5005.5     .12       0  5089.4     .05       0
Bank Sta=4981.8,5005.5
XS Rating Curve= 0 ,0
Exp/Cntr=0.3,0.1

Type RM Length L Ch R = 1 ,28500   ,500,500,500
BEGIN DESCRIPTION:
COLD CREEK 57.0
END DESCRIPTION:
XS GIS Cut Line= 3
      2747255.64      10294503.1      2746865.34     10294406.79
      2746805.68     10294053.09
#Sta/Elev= 30
    4598 1513.61  4616.1 1507.19  4657.6 1498.98  4670.1  1493.8  4680.4 1491.85
  4690.7 1488.04  4699.1 1480.96  4752.5 1464.92  4793.6 1459.95  4906.4 1453.88
  4917.2 1450.63  4947.9 1446.77  4967.1 1440.89  4967.6 1440.39    4991 1440.89
  5013.9 1440.93  5034.2 1443.53  5054.4 1449.21  5115.3 1455.56  5135.6 1461.26
  5155.9    1470  5204.9 1486.33    5210 1486.23  5216.7 1490.19  5265.4 1507.84
  5270.5 1508.31  5325.9 1528.89    5331 1528.67  5338.4 1532.89  5358.7 1540.08
#Mann= 3 ,-1 , 0
    4598     .12       0  4967.1     .07       0    4991     .12       0
Bank Sta=4967.1,4991
XS Rating Curve= 0 ,0
Exp/Cntr=0.3,0.1

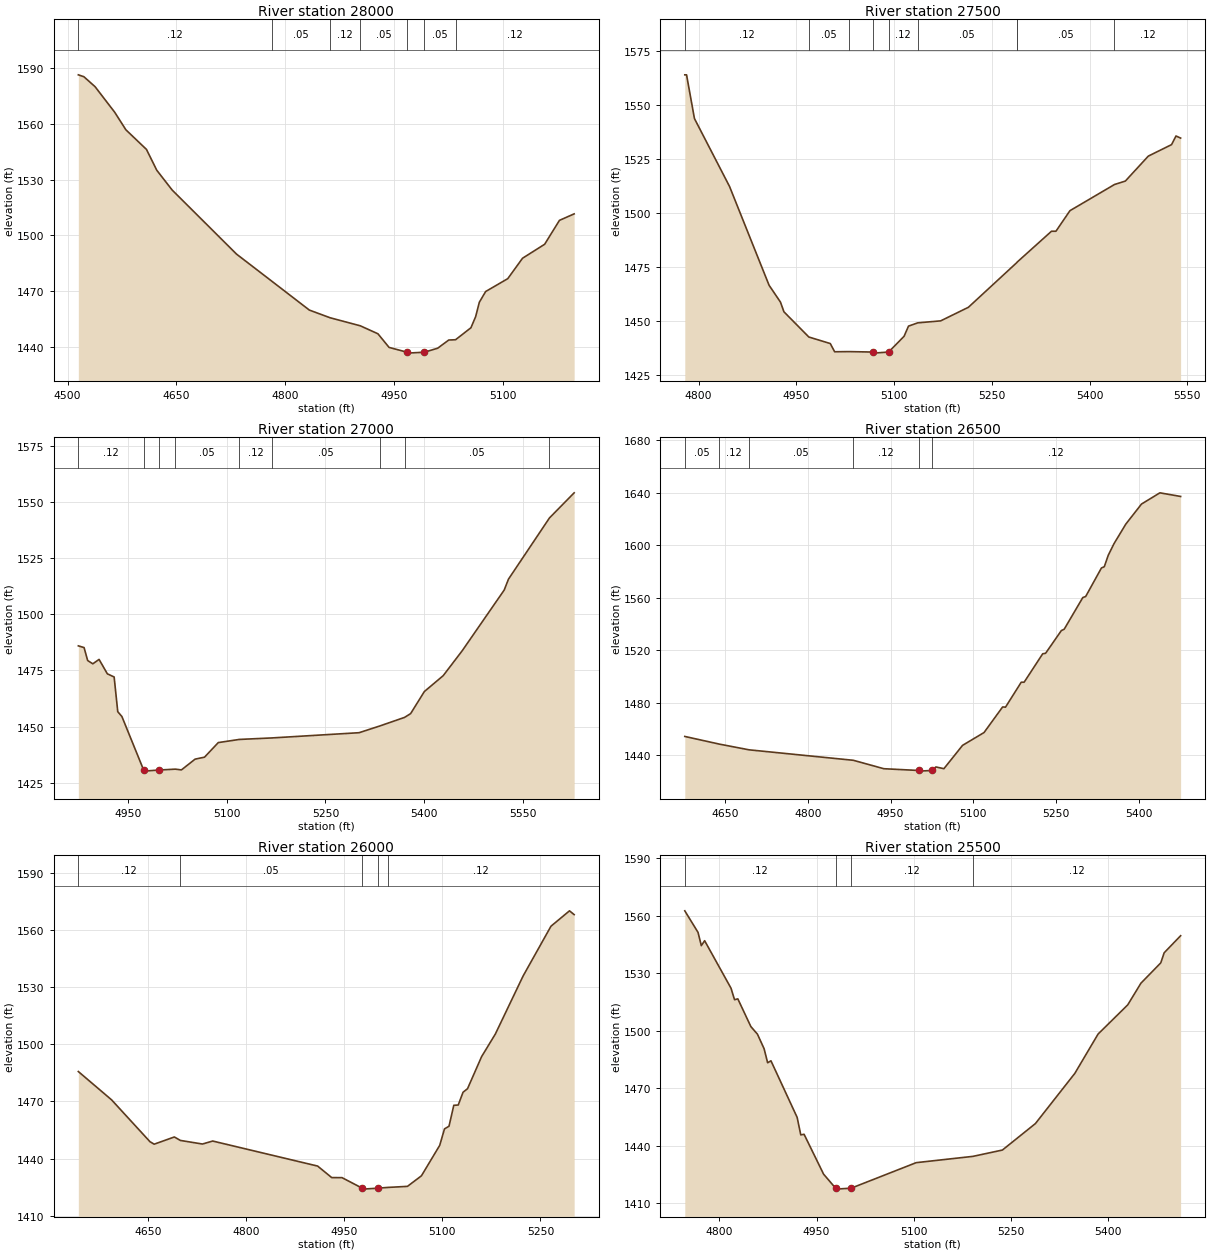
Type RM Length L Ch R = 1 ,28000   ,500,500,500
BEGIN DESCRIPTION:
COLD CREEK 56.0
END DESCRIPTION:
XS GIS Cut Line= 3
      2747505.67     10294503.09      2747251.06     10294090.06
      2747055.72     10294053.12
#Sta/Elev= 30
  4514.8  1586.4  4522.5 1585.37  4537.9 1580.01    4565 1566.23  4580.4 1556.79
  4608.8 1546.22    4623 1535.01  4644.3 1524.31    4733 1489.84  4781.4 1475.32
  4833.5 1459.67  4862.3 1455.51  4903.8  1451.2  4928.1  1446.9  4943.5 1439.55
  4968.2 1436.98  4968.7 1436.48  4992.2 1436.98  5010.5 1439.12  5025.8 1443.54
  5035.2 1443.69  5056.4 1450.15  5062.9 1456.12    5068 1463.89  5076.7 1469.67
  5107.2 1476.59  5127.6  1487.6  5158.1 1495.12  5178.5    1508  5198.8 1511.49
#Mann= 7 ,-1 , 0
  4514.8     .12       0  4781.4     .05       0  4862.3     .12       0
  4903.8     .05       0  4968.2     .05       0  4992.2     .05       0
  5035.2     .12       0
Bank Sta=4968.2,4992.2
XS Rating Curve= 0 ,0
Exp/Cntr=0.3,0.1

Type RM Length L Ch R = 1 ,27500   ,500,500,500
BEGIN DESCRIPTION:
COLD CREEK 55.0
END DESCRIPTION:
XS GIS Cut Line= 3
      2747405.69     10293453.09      2747323.56     10293658.37
      2746955.68     10294053.12
#Sta/Elev= 30
  4778.9 1563.92  4781.6 1563.92  4793.7 1543.69  4847.6 1512.23  4908.2 1466.55
  4925.7 1458.74    4931 1454.26  4969.2  1442.6  5002.1 1439.57  5008.8 1435.77
  5030.8 1435.84  5067.6 1435.64  5068.1 1435.14  5091.6 1435.64  5115.3 1442.93
  5122.1 1447.63  5136.3 1449.15  5171.5 1450.07    5214 1456.35  5288.3 1477.04
  5288.9 1477.29  5341.5 1491.54  5348.3 1491.54  5369.8 1501.05  5438.1 1513.16
  5454.8 1514.76    5490  1526.3  5525.7 1531.62  5532.5 1535.62  5539.6 1534.65
#Mann= 9 ,-1 , 0
  4778.9     .12       0  4969.2     .05       0  5030.8     .12       0
  5067.6     .03       0  5091.6     .12       0  5136.3     .05       0
  5288.3     .12       0  5288.9     .05       0  5438.1     .12       0
Bank Sta=5067.6,5091.6
XS Rating Curve= 0 ,0
Exp/Cntr=0.3,0.1

Type RM Length L Ch R = 1 ,27000   ,500,500,500
BEGIN DESCRIPTION:
COLD CREEK 54.0
END DESCRIPTION:
XS GIS Cut Line= 3
      2747055.66     10293303.12      2746942.08     10293356.03
      2746455.68     10293753.11
#Sta/Elev= 30
  4874.7 1485.93  4883.4 1485.18  4888.9 1479.39  4896.7 1477.94  4906.2  1479.9
  4918.8 1473.48  4929.1 1472.07  4934.6 1456.62  4940.9 1454.46  4973.9 1430.65
  4974.4 1430.15  4997.9 1430.65  5021.9 1431.03  5031.3 1430.69  5052.1 1435.49
  5066.4 1436.37  5087.3 1442.86  5119.2 1444.26  5169.4 1444.94  5301.2 1447.26
  5332.9 1450.28  5370.3 1454.08  5379.5 1455.76  5400.3 1465.58    5429 1472.67
  5457.7  1483.7  5521.6 1510.77  5528.1 1515.62  5590.4  1542.9  5627.9 1554.08
#Mann= 9 ,-1 , 0
  4874.7     .12       0  4973.9     .07       0  4997.9     .12       0
  5021.9     .05       0  5119.2     .12       0  5169.4     .05       0
  5332.9     .12       0  5370.3     .05       0  5590.4     .12       0
Bank Sta=4973.9,4997.9
XS Rating Curve= 0 ,0
Exp/Cntr=0.3,0.1

Type RM Length L Ch R = 1 ,26500   ,500,500,500
BEGIN DESCRIPTION:
COLD CREEK 53.0
END DESCRIPTION:
XS GIS Cut Line= 3
       2746905.7     10293103.11      2746486.36      10293155.5
      2746029.67     10293286.84
#Sta/Elev= 30
  4577.4 1454.41  4640.2 1448.54  4693.9  1444.2  4882.6 1436.23  4937.8 1429.81
  5000.8 1428.47  5001.3 1427.97  5024.9 1428.47  5031.9 1431.16  5046.6 1429.84
  5080.3  1447.6  5119.2 1457.37  5152.9 1476.89  5158.1 1476.73  5186.6 1495.74
  5191.8 1495.73  5225.5 1517.44  5230.7  1517.8  5259.2 1535.08  5264.4 1536.15
  5298.1 1560.29  5303.3 1561.09  5331.8 1582.81    5337 1583.79  5344.1 1592.45
  5354.5  1601.3  5375.9 1616.24  5404.4 1631.57  5437.7 1640.11  5475.2 1637.34
#Mann= 6 ,-1 , 0
  4577.4     .05       0  4640.2     .12       0  4693.9     .05       0
  4882.6     .12       0  5000.8     .07       0  5024.9     .12       0
Bank Sta=5000.8,5024.9
XS Rating Curve= 0 ,0
Exp/Cntr=0.3,0.1

Type RM Length L Ch R = 1 ,26000   ,500,500,500
BEGIN DESCRIPTION:
COLD CREEK 52.0
END DESCRIPTION:
XS GIS Cut Line= 3
       2747155.7     10293053.12      2746762.16     10292822.77
      2746555.66     10292603.09
#Sta/Elev= 30
    4544  1485.7  4594.8 1470.83  4653.5 1448.83  4659.9 1447.54  4690.7 1451.33
  4699.9 1449.51  4733.6 1447.62  4749.3 1449.19  4909.6 1436.04  4931.1 1429.99
  4946.8 1429.97  4977.7 1424.43  4978.2 1423.93  5001.8 1424.43  5016.6 1424.82
  5046.8 1425.38  5068.2 1430.93  5096.1 1446.92  5103.4 1455.57  5110.3 1456.96
  5117.6 1467.95  5124.4 1468.12  5131.7  1474.8  5138.6 1476.68  5160.1 1493.53
  5181.1  1505.4  5223.6 1535.95  5266.1 1562.04  5294.4 1570.12  5301.5 1568.13
#Mann= 5 ,-1 , 0
    4544     .12       0  4699.9     .05       0  4977.7     .03       0
  5001.8     .05       0  5016.6     .12       0
Bank Sta=4977.7,5001.8
XS Rating Curve= 0 ,0
Exp/Cntr=0.3,0.1

Type RM Length L Ch R = 1 ,25500   ,500,500,500
BEGIN DESCRIPTION:
COLD CREEK 51.0
END DESCRIPTION:
XS GIS Cut Line= 3
      2747355.66     10292453.12      2747107.22      10292502.5
      2746605.72     10292603.11
#Sta/Elev= 30
  4746.7 1562.61  4767.1 1551.37  4772.2 1544.43  4777.3 1547.03    4818 1522.23
  4823.4 1516.25  4828.5 1516.68  4848.6 1502.22  4858.8 1498.23    4869 1490.68
  4874.5 1483.33  4879.6 1484.36    4920 1454.83  4925.6 1445.71  4930.7 1446.01
  4960.8 1425.21  4979.3  1417.9  4979.8  1417.4  5003.4  1417.9  5103.6 1431.21
  5191.1 1434.49  5236.6 1437.79  5287.5  1451.6  5348.3 1477.79  5384.2 1498.32
  5429.9 1513.53  5450.3 1524.86  5480.9 1535.46  5486.1 1540.71  5511.5 1549.62
#Mann= 4 ,-1 , 0
  4746.7     .12       0  4979.3     .03       0  5003.4     .12       0
  5191.1     .12       0
Bank Sta=4979.3,5003.4
XS Rating Curve= 0 ,0
Exp/Cntr=0.3,0.1

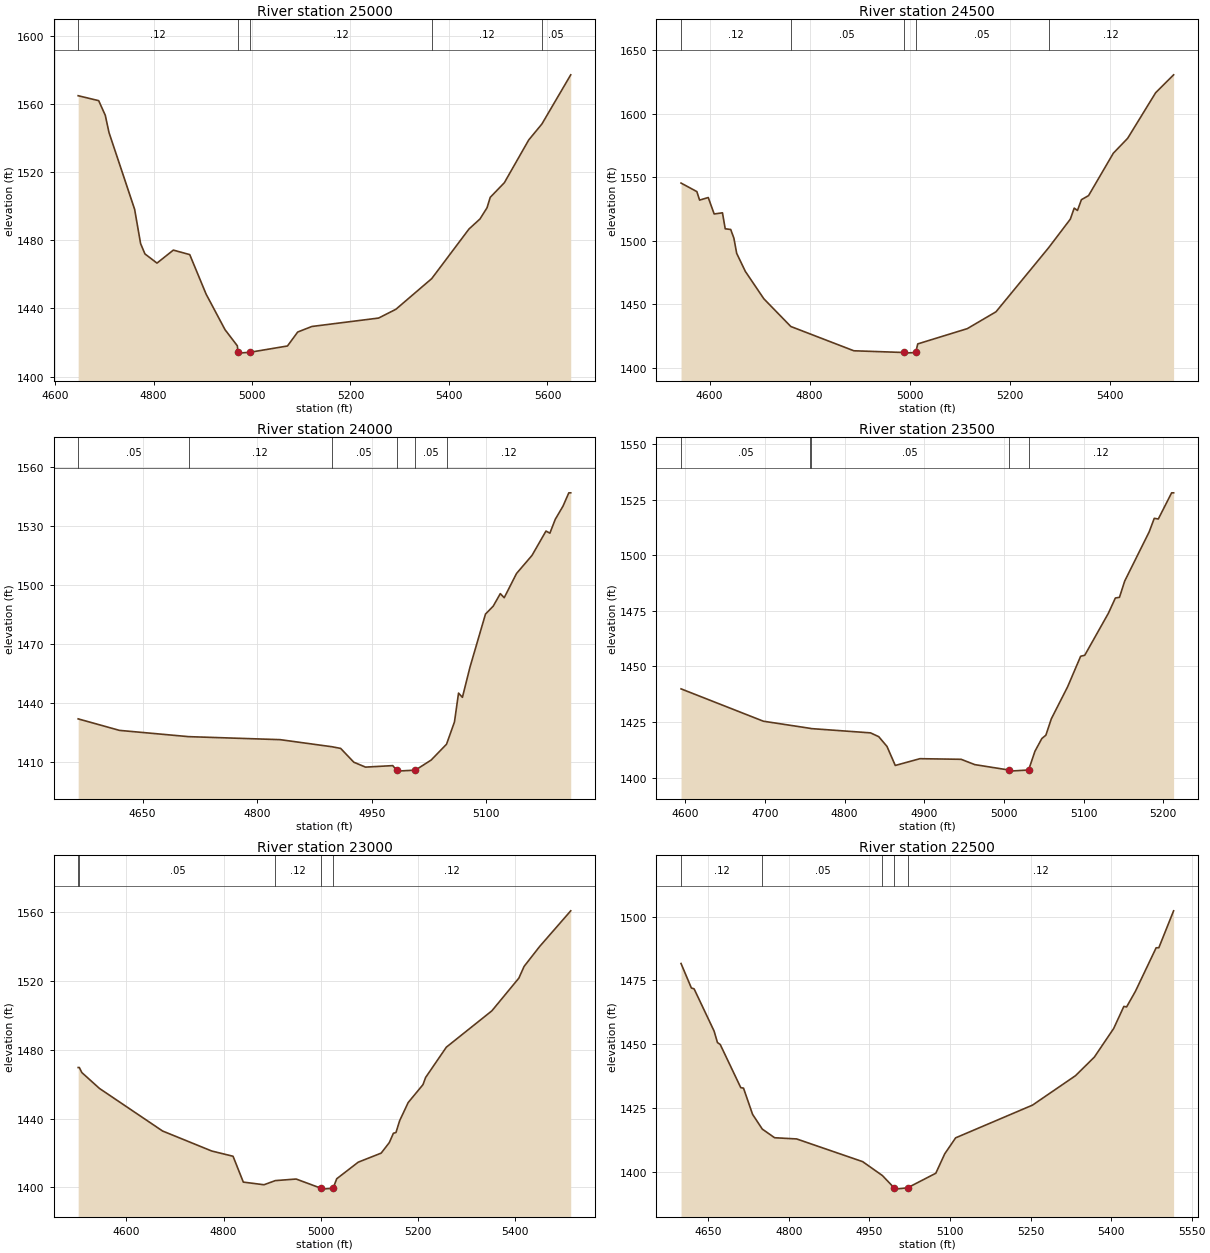
Type RM Length L Ch R = 1 ,25000   ,500,500,500
BEGIN DESCRIPTION:
COLD CREEK 50.0
END DESCRIPTION:
XS GIS Cut Line= 3
      2746955.69     10291753.11      2746855.44     10292091.68
      2746355.71     10292503.09
#Sta/Elev= 30
  4646.9 1565.03  4688.6 1562.12    4702 1553.51  4709.5 1543.42  4761.6 1498.23
  4773.7 1478.12  4782.5 1472.06    4807 1466.65  4840.2 1474.29  4873.5 1471.65
  4906.8 1448.39  4945.2 1427.51  4970.2 1418.03  4971.6 1414.24  4972.1 1413.74
  4995.8 1414.24    5072 1417.94  5092.8 1426.14  5121.5  1429.4  5257.1 1434.35
  5292.2 1439.51    5365 1457.54  5440.7  1486.7    5463  1492.6  5477.3 1499.18
  5483.8  1505.3  5512.5 1513.91    5562 1539.03  5588.7 1548.39  5647.3 1577.31
#Mann= 5 ,-1 , 0
  4646.9     .12       0  4971.6     .03       0  4995.8     .12       0
    5365     .12       0  5588.7     .05       0
Bank Sta=4971.6,4995.8
XS Rating Curve= 0 ,0
Exp/Cntr=0.3,0.1

Type RM Length L Ch R = 1 ,24500   ,500,500,500
BEGIN DESCRIPTION:
COLD CREEK 49.0
END DESCRIPTION:
XS GIS Cut Line= 3
      2746805.71      10291753.1      2746391.58     10291946.13
      2746055.68     10292353.12
#Sta/Elev= 30
  4543.1 1545.28  4574.7 1538.58  4580.2 1531.88  4597.5  1533.9  4609.3 1520.97
  4625.9 1521.87  4631.4  1509.3  4642.4 1508.76  4648.8 1501.83  4654.3 1489.99
  4671.7 1475.73  4708.6 1454.24  4762.5 1432.42  4888.5 1413.31  4987.9 1411.96
  4988.4 1411.46  5012.1 1411.96  5016.3 1418.72  5115.3 1430.73  5172.7    1444
  5277.9 1494.41  5321.2 1516.86    5329 1525.58  5335.5 1523.73  5343.4 1532.19
  5357.7 1535.42  5407.2 1568.78  5435.9 1580.53  5491.8 1616.38  5527.7 1630.46
#Mann= 5 ,-1 , 0
  4543.1     .12       0  4762.5     .05       0  4987.9     .05       0
  5012.1     .05       0  5277.9     .12       0
Bank Sta=4987.9,5012.1
XS Rating Curve= 0 ,0
Exp/Cntr=0.3,0.1

Type RM Length L Ch R = 1 ,24000   ,500,500,500
BEGIN DESCRIPTION:
COLD CREEK 48.0
END DESCRIPTION:
XS GIS Cut Line= 3
      2746405.71      10291453.1       2746013.1     10291639.01
      2745805.69     10291603.11
#Sta/Elev= 30
  4565.6 1431.99  4619.7 1426.14  4710.1 1422.96    4830 1421.43    4898 1417.82
  4909.3 1416.98  4926.5 1409.97  4941.8 1407.48  4977.5 1408.24  4982.4 1405.94
  4982.9 1405.44  5007.1 1405.94  5027.8 1411.08  5047.9 1419.12  5058.3 1430.46
  5063.6 1445.08  5068.7 1442.94  5078.6 1458.28  5098.9 1485.24    5109 1489.25
  5118.3 1495.63  5123.4 1493.54  5139.5 1505.84  5159.8 1515.05  5178.1 1527.42
  5183.2 1526.34  5190.2 1533.34  5200.4 1540.09    5208 1546.84  5210.5 1546.84
#Mann= 6 ,-1 , 0
  4565.6     .05       0  4710.1     .12       0    4898     .05       0
  4982.4     .05       0  5007.1     .05       0  5047.9     .12       0
Bank Sta=4982.4,5007.1
XS Rating Curve= 0 ,0
Exp/Cntr=0.3,0.1

Type RM Length L Ch R = 1 ,23500   ,500,500,500
BEGIN DESCRIPTION:
COLD CREEK 47.0
END DESCRIPTION:
XS GIS Cut Line= 3
      2746455.64      10291253.1       2746063.8     10291149.14
      2745855.73     10291103.12
#Sta/Elev= 30
  4594.6 1439.89    4698 1425.33  4756.4 1422.14  4758.4    1422  4832.5 1420.09
  4842.9 1418.36  4853.2 1413.98  4863.6 1405.42  4894.6 1408.47  4946.3 1408.19
  4963.4  1405.8  5006.2 1403.37  5006.7 1402.87    5031 1403.37    5039 1411.82
  5047.6 1417.52  5052.7 1419.04  5059.5 1426.37    5080 1440.81  5096.4 1454.57
  5101.5    1455  5131.2 1473.91    5140 1480.78  5145.1 1481.07  5151.7  1488.4
  5182.4 1510.52  5188.8 1516.62  5193.9 1516.33  5210.6  1528.1  5213.1  1528.1
#Mann= 5 ,-1 , 0
  4594.6     .05       0  4756.4     .12       0  4758.4     .05       0
  5006.2     .05       0    5031     .12       0
Bank Sta=5006.2,5031
XS Rating Curve= 0 ,0
Exp/Cntr=0.3,0.1

Type RM Length L Ch R = 1 ,23000   ,500,500,500
BEGIN DESCRIPTION:
COLD CREEK 46.0
END DESCRIPTION:
XS GIS Cut Line= 3
      2746655.69     10290953.12      2746237.74     10290680.69
       2745755.7     10290503.12
#Sta/Elev= 30
  4501.1 1469.74  4503.5 1469.74  4508.7  1466.8  4544.9 1457.57  4674.6  1432.8
  4775.7 1421.15  4819.5  1418.1  4840.6 1403.06  4883.1 1401.52  4906.4 1403.93
  4949.3 1404.84  5000.4 1399.47  5000.9 1398.97  5025.2 1399.47  5032.6 1404.99
  5076.8 1414.65    5124 1419.93  5140.7 1426.04  5149.1 1431.49  5154.4 1431.89
    5162  1438.8  5179.5 1449.35    5210  1459.8  5215.3 1463.92    5258 1481.59
  5351.6 1502.75  5407.1 1521.79  5417.8 1528.59  5449.8 1540.19  5513.7 1560.95
#Mann= 5 ,-1 , 0
  4501.1     .12       0  4503.5     .05       0  4906.4     .12       0
  5000.4     .07       0  5025.2     .12       0
Bank Sta=5000.4,5025.2
XS Rating Curve= 0 ,0
Exp/Cntr=0.3,0.1

Type RM Length L Ch R = 1 ,22500   ,500,500,500
BEGIN DESCRIPTION:
COLD CREEK 45.0
END DESCRIPTION:
XS GIS Cut Line= 3
      2746805.69     10290303.11       2746414.7      10290215.9
      2745905.72     10290303.11
#Sta/Elev= 30
  4599.4 1481.63  4618.6 1472.08  4623.7 1471.73  4660.9 1455.25  4667.2 1450.75
  4672.3 1450.01  4710.6 1433.13  4715.7 1432.94  4732.6 1422.68  4750.7 1416.93
  4773.6 1413.56  4814.6 1413.09  4937.5 1404.22  4974.3 1398.78  4996.1 1393.98
  4996.6 1393.48    5021 1393.98  5073.7 1399.69  5090.3 1407.27  5110.6 1413.52
  5253.8 1426.31  5333.8 1437.81  5368.9 1445.08  5404.8 1456.24  5423.8 1464.88
  5428.9 1464.68  5445.4 1470.81  5483.9 1487.78  5488.9  1487.8  5516.4 1502.22
#Mann= 5 ,-1 , 0
  4599.4     .12       0  4750.7     .05       0  4974.3     .12       0
  4996.1     .07       0    5021     .12       0
Bank Sta=4996.1,5021
XS Rating Curve= 0 ,0
Exp/Cntr=0.3,0.1