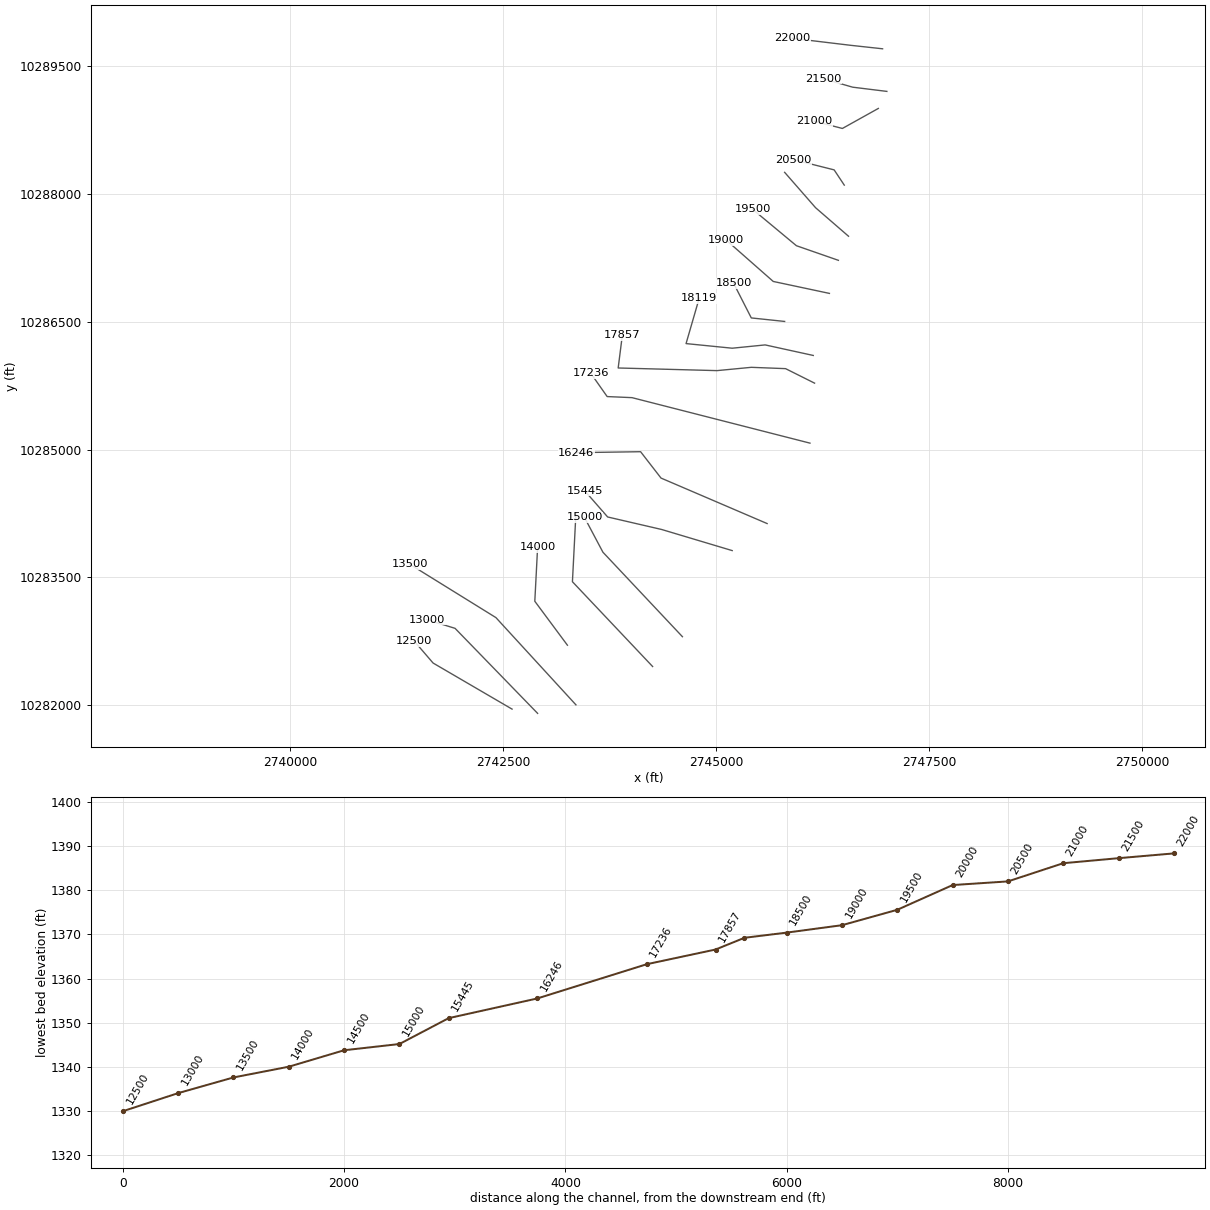
HEC-RAS study COLD CREEK.prj: COLD CREEK Base Level Engineering

--- COLD CREEK.g01 (geometry) --- (continued)

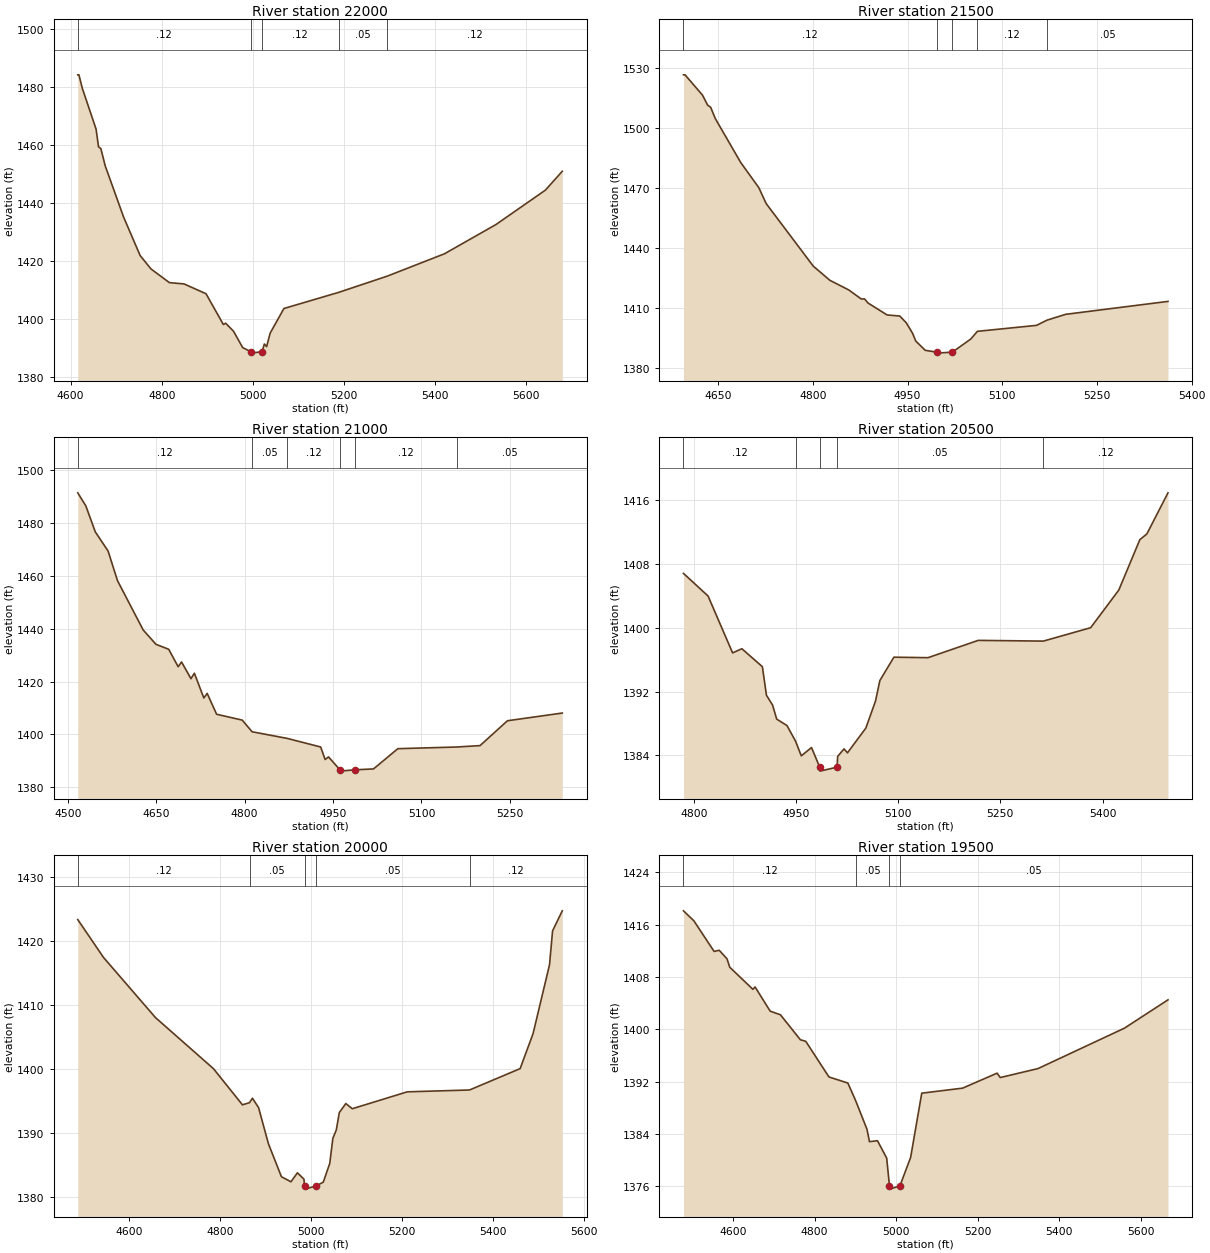
Type RM Length L Ch R = 1 ,22000   ,500,500,500
BEGIN DESCRIPTION:
COLD CREEK 44.0
END DESCRIPTION:
XS GIS Cut Line= 3
      2746955.65     10289703.12      2746573.62     10289744.81
      2745898.87     10289825.87
#Sta/Elev= 30
  4615.7 1484.11  4618.2 1484.11  4625.7 1479.47  4655.9 1465.43  4661.3 1459.36
  4666.4 1458.73    4676 1452.78  4716.3 1435.19  4752.7 1421.92  4776.6  1417.3
  4816.9 1412.61  4849.1 1412.16  4897.3 1408.79  4935.4  1398.2  4940.4 1398.65
  4957.7 1395.88  4977.8 1390.26  4995.5 1388.85    4996 1388.35  5020.5 1388.85
  5025.4 1391.48  5030.4 1390.61  5038.2 1395.24  5068.4 1403.71  5188.3 1409.24
  5295.1 1414.83  5420.9 1422.53  5533.7 1432.57  5642.5 1444.43  5679.6 1450.92
#Mann= 5 ,-1 , 0
  4615.7     .12       0  4995.5     .07       0  5020.5     .12       0
  5188.3     .05       0  5295.1     .12       0
Bank Sta=4995.5,5020.5
XS Rating Curve= 0 ,0
Exp/Cntr=0.3,0.1

Type RM Length L Ch R = 1 ,21500   ,500,500,500
BEGIN DESCRIPTION:
COLD CREEK 43.0
END DESCRIPTION:
XS GIS Cut Line= 3
       2747005.7     10289203.11      2746603.94     10289252.62
      2746255.65     10289353.12
#Sta/Elev= 30
  4595.2 1526.44  4597.7 1526.44  4625.4 1516.26  4633.3 1511.36  4638.3 1510.19
  4645.6 1504.57  4685.9 1482.59  4714.5 1470.02  4726.2 1462.05  4800.7  1430.8
    4827  1423.7  4857.2 1418.82  4876.8 1414.34  4881.9  1414.4  4887.4 1412.34
  4917.6 1406.37  4937.8 1405.81  4947.9 1402.49  4957.9 1397.28  4963.1  1393.3
  4978.1 1388.67  4996.1 1387.77  4996.6 1387.27  5021.1 1387.77  5050.2 1394.32
  5060.7 1398.17  5154.3 1401.15    5171 1403.77  5200.6 1406.68  5362.5 1413.14
#Mann= 5 ,-1 , 0
  4595.2     .12       0  4996.1     .07       0  5021.1     .12       0
  5060.7     .12       0    5171     .05       0
Bank Sta=4996.1,5021.1
XS Rating Curve= 0 ,0
Exp/Cntr=0.3,0.1

Type RM Length L Ch R = 1 ,21000   ,500,500,500
BEGIN DESCRIPTION:
COLD CREEK 42.0
END DESCRIPTION:
XS GIS Cut Line= 3
      2746905.65     10289003.09      2746483.65     10288768.14
      2746155.68     10288853.11
#Sta/Elev= 30
    4517 1491.49  4530.7 1486.54  4546.7 1476.72  4568.4 1469.47  4584.4 1458.24
  4627.9 1439.59  4649.6 1434.14  4671.3 1432.25  4687.3 1425.65    4693 1427.47
    4709 1421.13  4714.8 1423.19  4730.8 1413.82  4736.5 1415.56  4752.5 1407.66
  4795.9 1405.45  4812.7 1401.03  4872.4 1398.51    4929 1395.27  4936.6 1390.52
  4942.3 1391.52  4961.7 1386.63  4962.2 1386.13  4986.8 1386.63  5018.6 1386.96
  5059.9 1394.63  5160.2 1395.26  5199.3 1395.79  5245.8  1405.2  5338.8 1408.12
#Mann= 6 ,-1 , 0
    4517     .12       0  4812.7     .05       0  4872.4     .12       0
  4961.7     .07       0  4986.8     .12       0  5160.2     .05       0
Bank Sta=4961.7,4986.8
XS Rating Curve= 0 ,0
Exp/Cntr=0.3,0.1

Type RM Length L Ch R = 1 ,20500   ,500,500,500
BEGIN DESCRIPTION:
COLD CREEK 41.0
END DESCRIPTION:
XS GIS Cut Line= 3
      2746505.71     10288103.07      2746386.66      10288282.1
      2745905.65     10288403.12
#Sta/Elev= 30
    4785 1406.83  4821.1 1403.99  4857.1 1396.85  4870.7 1397.37  4900.8 1395.12
  4906.8 1391.53  4915.8  1390.3  4921.8 1388.54  4936.9 1387.73  4949.5 1385.77
  4957.9 1383.93  4972.9 1384.97  4984.9 1382.51  4985.4 1382.01  5010.4 1382.51
  5011.3 1383.86  5020.6  1384.8  5025.7 1384.31  5052.6 1387.41  5066.8  1390.8
  5073.2 1393.38  5093.8 1396.31  5143.9 1396.25  5217.5 1398.42  5313.1 1398.33
  5382.5 1400.01  5423.8 1404.73  5454.7 1411.06    5465 1411.78    5496 1416.94
#Mann= 5 ,-1 , 0
    4785     .12       0  4949.5     .05       0  4984.9     .05       0
  5010.4     .05       0  5313.1     .12       0
Bank Sta=4984.9,5010.4
XS Rating Curve= 0 ,0
Exp/Cntr=0.3,0.1

Type RM Length L Ch R = 1 ,20000   ,500,500,500
BEGIN DESCRIPTION:
COLD CREEK 40.0
END DESCRIPTION:
XS GIS Cut Line= 3
      2746555.68     10287503.11       2746168.7     10287838.06
      2745805.69      10288253.1
#Sta/Elev= 30
  4488.2 1423.32  4544.7  1417.4  4658.7    1408    4786 1400.01  4849.6 1394.36
  4865.1  1394.7  4871.5 1395.39    4885 1393.92  4906.6 1388.27  4935.1 1383.12
    4956 1382.33  4970.2 1383.73  4984.5 1382.74  4985.9 1381.68  4986.4 1381.18
  5011.5 1381.68    5027 1382.28  5041.2 1385.22  5047.9 1389.11  5055.5 1390.43
  5062.1 1393.14  5076.4 1394.56  5090.6 1393.75  5211.1 1396.39  5347.9 1396.68
  5458.9 1400.02  5487.3 1405.49  5523.4 1416.27  5530.1 1421.56  5551.4 1424.69
#Mann= 5 ,-1 , 0
  4488.2     .12       0  4865.1     .05       0  4985.9     .05       0
  5011.5     .05       0  5347.9     .12       0
Bank Sta=4985.9,5011.5
XS Rating Curve= 0 ,0
Exp/Cntr=0.3,0.1

Type RM Length L Ch R = 1 ,19500   ,500,500,500
BEGIN DESCRIPTION:
COLD CREEK 39.0
END DESCRIPTION:
XS GIS Cut Line= 3
      2746436.71     10287220.43      2745943.79     10287391.92
      2745430.94     10287818.38
#Sta/Elev= 30
  4478.1 1418.13  4503.6 1416.61  4553.3 1411.92  4565.8  1412.1  4585.1 1410.78
  4591.6 1409.51  4648.5 1406.13  4653.8 1406.49  4690.9 1402.79    4716 1402.24
  4765.1 1398.41  4778.2 1398.18  4835.1 1392.73  4881.5  1391.8  4900.5 1389.13
  4928.4 1384.73  4934.5 1382.84  4954.2 1382.98  4976.8 1380.32  4983.6 1376.08
  4984.1 1375.58  5009.2 1376.08  5035.5 1380.42  5062.8 1390.25  5163.1 1391.02
  5247.7 1393.31  5255.5 1392.64    5348 1394.01  5560.2 1400.19    5667 1404.52
#Mann= 4 ,-1 , 0
  4478.1     .12       0  4900.5     .05       0  4983.6     .05       0
  5009.2     .05       0
Bank Sta=4983.6,5009.2
XS Rating Curve= 0 ,0
Exp/Cntr=0.3,0.1

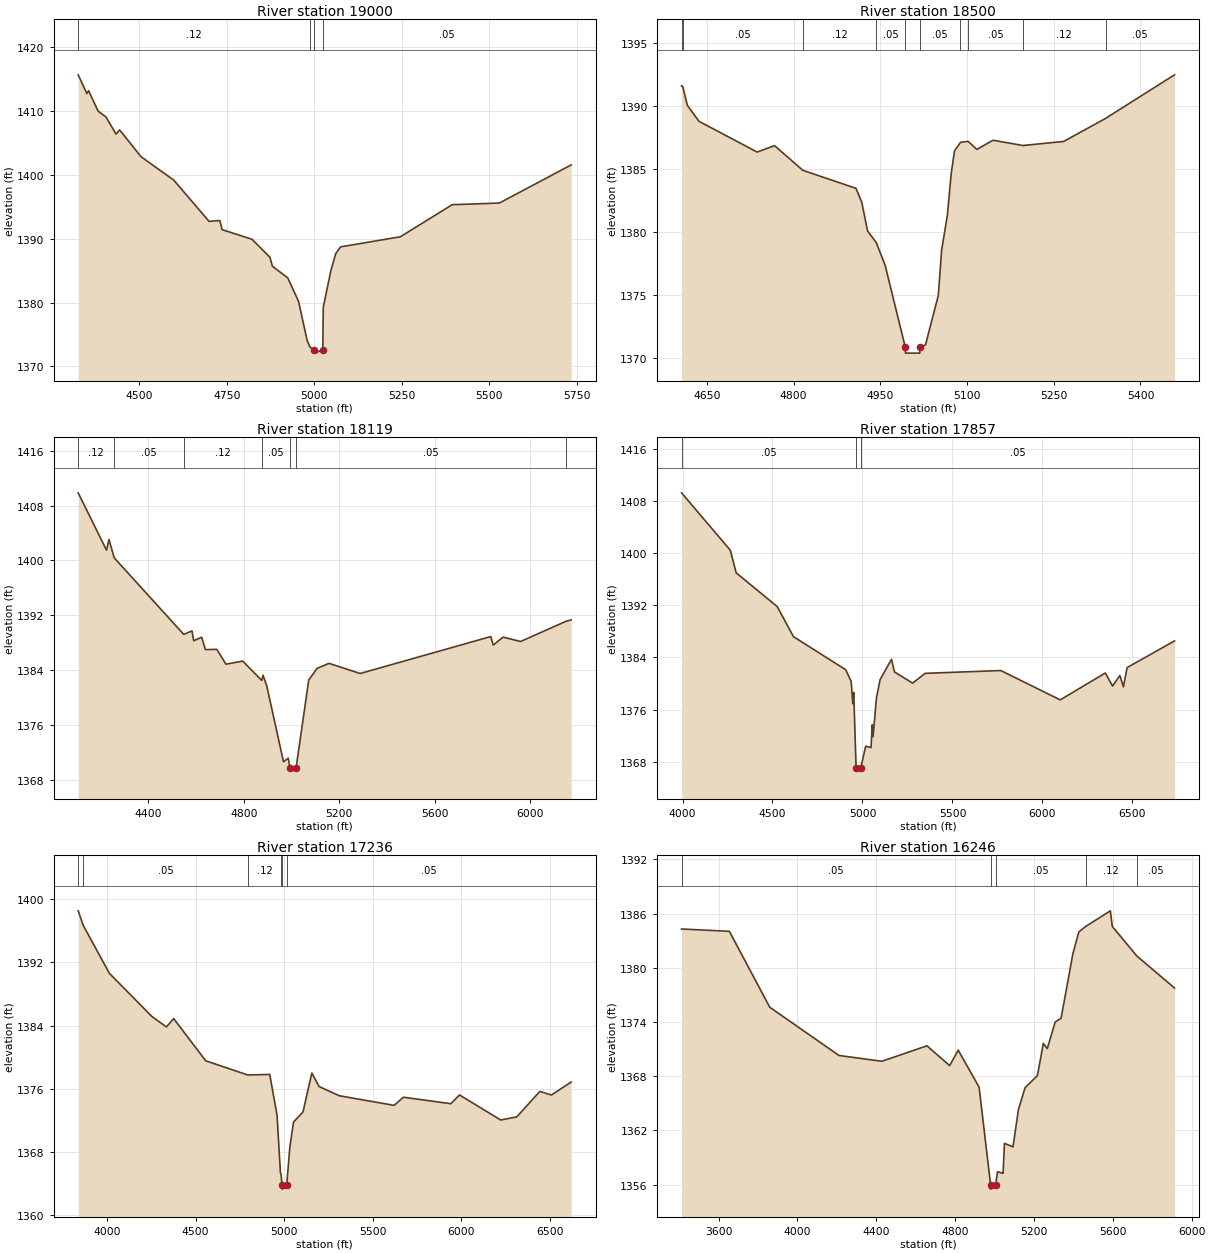
Type RM Length L Ch R = 1 ,19000   ,500,500,500
BEGIN DESCRIPTION:
COLD CREEK 38.0
END DESCRIPTION:
XS GIS Cut Line= 3
      2746331.39     10286832.23      2745671.84     10286972.48
      2745120.65     10287457.34
#Sta/Elev= 30
  4325.7 1415.62  4350.4  1412.7  4355.5 1413.13  4382.7 1409.94  4405.1 1409.03
  4433.8 1406.35    4444 1407.01  4505.3 1402.81  4598.4 1399.17  4699.6  1392.7
  4730.3 1392.83    4737  1391.4  4822.3  1389.9  4873.4 1387.09  4880.7 1385.68
  4924.5 1383.85  4955.2  1380.2  4979.9 1374.06  4988.2 1373.02  4998.8 1372.59
  4999.3 1372.09  5024.5 1372.59  5025.9 1379.27  5047.7 1385.03  5061.5 1387.65
  5075.3 1388.71    5246 1390.29  5394.4 1395.31  5528.8 1395.56  5734.1 1401.53
#Mann= 4 ,-1 , 0
  4325.7     .12       0  4988.2     .05       0  4998.8     .05       0
  5024.5     .05       0
Bank Sta=4998.8,5024.5
XS Rating Curve= 0 ,0
Exp/Cntr=0.3,0.1

Type RM Length L Ch R = 1 ,18500   ,381,381,381
BEGIN DESCRIPTION:
COLD CREEK 37.0
END DESCRIPTION:
XS GIS Cut Line= 3
      2745805.73     10286503.11      2745414.19     10286544.31
      2745205.68     10286953.11
#Sta/Elev= 30
  4606.3 1391.61  4608.2 1391.61  4616.4 1390.07  4636.5 1388.81  4737.1 1386.37
  4767.2 1386.88  4816.1 1384.92    4908 1383.49  4918.1 1382.37  4928.1  1380.1
    4943 1379.19  4958.3  1377.4  4993.1 1370.91  4993.6 1370.41  5018.3 1370.41
  5018.8 1370.91  5028.2 1371.06  5050.4 1374.99  5056.1 1378.57    5066 1381.34
  5072.7 1384.66  5078.3 1386.45  5088.7 1387.14  5101.9 1387.22  5117.1 1386.58
    5145 1387.31  5196.6 1386.89  5267.1 1387.21  5339.6 1389.04  5458.9  1392.5
#Mann= 10 ,-1 , 0
  4606.3     .12       0  4608.2     .05       0  4816.1     .12       0
    4943     .05       0  4993.1     .05       0  5018.8     .05       0
  5088.7     .12       0  5101.9     .05       0  5196.6     .12       0
  5339.6     .05       0
Bank Sta=4993.1,5018.8
XS Rating Curve= 0 ,0
Exp/Cntr=0.3,0.1

Type RM Length L Ch R = 1 ,18119   ,262,262,262
BEGIN DESCRIPTION:
Mapping XS 963a4e6e
END DESCRIPTION:
XS GIS Cut Line= 5
      2746141.71     10286103.88      2745576.87     10286227.68
      2745190.01     10286188.99       2744648.4     10286243.16
      2744803.15     10286777.03
#Sta/Elev= 30
  4105.8 1409.86  4224.6 1401.49  4234.8 1403.04  4257.1 1400.36  4548.5  1389.2
  4582.9 1389.71  4590.3 1388.27  4623.8 1388.78  4639.3 1386.98  4687.2 1387.01
  4725.4 1384.85  4795.8  1385.3  4875.4 1382.48    4881 1383.23  4896.3 1381.71
  4966.6 1370.61  4986.7 1371.13  4993.9 1369.74  4994.4 1369.24  5019.7 1369.74
  5072.5 1382.53  5107.3 1384.23  5157.6 1384.97  5288.2 1383.49  5835.7 1388.88
  5846.2 1387.64  5887.8  1388.8  5960.7 1388.16  6150.9  1391.1    6173 1391.32
#Mann= 7 ,-1 , 0
  4105.8     .12       0  4257.1     .05       0  4548.5     .12       0
  4875.4     .05       0  4993.9     .03       0  5019.7     .05       0
  6150.9     .12       0
Bank Sta=4993.9,5019.7
XS Rating Curve= 0 ,0
Exp/Cntr=0.3,0.1

Type RM Length L Ch R = 1 ,17857   ,621,621,621
BEGIN DESCRIPTION:
Mapping XS 36ebee13
END DESCRIPTION:
XS GIS Cut Line= 6
      2746157.17     10285778.91      2745816.72     10285949.14
      2745414.39     10285964.62      2745012.05     10285925.93
      2743851.47     10285956.88      2743900.72     10286344.61
#Sta/Elev= 30
  3994.6 1409.24  4265.7 1400.44  4298.1 1396.98  4526.4  1391.8  4616.5 1387.19
  4907.2 1382.12  4937.3 1380.31  4946.3 1376.92  4951.3 1378.63  4964.6 1367.08
  4965.1 1366.58  4990.4 1367.08  5017.7 1370.39  5047.8  1370.2  5053.8 1373.68
  5058.8 1371.86  5077.9 1377.86    5098 1380.61  5161.3 1383.72  5177.7 1381.79
  5278.5 1380.07  5348.5 1381.57  5768.6    1382  6098.8  1377.5  6349.3 1381.62
  6389.7 1379.62    6430 1381.24  6450.1  1379.5  6470.3 1382.45  6733.9 1386.54
#Mann= 3 ,-1 , 0
  3994.6     .05       0  4964.6     .05       0  4990.4     .05       0
Bank Sta=4964.6,4990.4
XS Rating Curve= 0 ,0
Exp/Cntr=0.3,0.1

Type RM Length L Ch R = 1 ,17236   ,990,990,990
BEGIN DESCRIPTION:
Mapping XS 05c1839f
END DESCRIPTION:
XS GIS Cut Line= 4
      2746103.01     10285074.84      2744013.95     10285608.71
       2743722.1     10285621.39      2743530.11     10285894.19
#Sta/Elev= 30
  3837.5 1398.54  3866.5 1396.67  4013.8 1390.61  4253.7 1385.14  4335.4 1383.82
  4376.2 1384.88  4557.2 1379.53  4794.2 1377.73  4918.5  1377.8  4959.8 1372.61
  4978.4 1365.42  4982.6 1365.09  4988.2 1363.76  4988.7 1363.26    5014 1363.76
    5032  1368.6  5052.7 1371.76  5106.1 1373.05  5155.9 1377.97  5197.2 1376.26
  5310.7  1375.1  5620.3 1373.88  5672.6 1374.91  5940.3 1374.09    5989  1375.2
  6222.2 1372.02  6312.4 1372.42  6442.7 1375.65    6508 1375.19  6619.4 1376.84
#Mann= 6 ,-1 , 0
  3837.5     .12       0  3866.5     .05       0  4794.2     .12       0
  4982.6     .05       0  4988.2     .05       0    5014     .05       0
Bank Sta=4988.2,5014
XS Rating Curve= 0 ,0
Exp/Cntr=0.3,0.1

Type RM Length L Ch R = 1 ,16246   ,801,801,801
BEGIN DESCRIPTION:
Mapping XS 6fcf7ce0
END DESCRIPTION:
XS GIS Cut Line= 4
      2745600.09      10284130.9      2744354.39     10284664.77
      2744114.54     10284974.26      2743360.15     10284962.97
#Sta/Elev= 30
  3411.8 1384.29  3654.5 1384.03  3859.4 1375.63  4210.8 1370.29  4428.4 1369.65
  4656.9 1371.36  4772.2 1369.17  4815.6 1370.88  4921.6 1366.78  4979.8    1356
  4980.3  1355.5  5005.7    1356  5014.8 1357.42  5043.3 1357.25  5050.1 1360.57
  5093.6 1360.17  5120.8 1364.27  5154.7 1366.72  5217.5 1368.07  5247.5 1371.63
  5267.5 1371.05  5307.5 1373.99  5337.5 1374.41  5397.5 1381.56  5427.5 1383.96
  5462.4 1384.57  5587.5  1386.3  5597.5 1384.57  5722.3 1381.29  5913.1 1377.76
#Mann= 5 ,-1 , 0
  3411.8     .05       0  4979.8     .05       0  5005.7     .05       0
  5462.4     .12       0  5722.3     .05       0
Bank Sta=4979.8,5005.7
XS Rating Curve= 0 ,0
Exp/Cntr=0.3,0.1

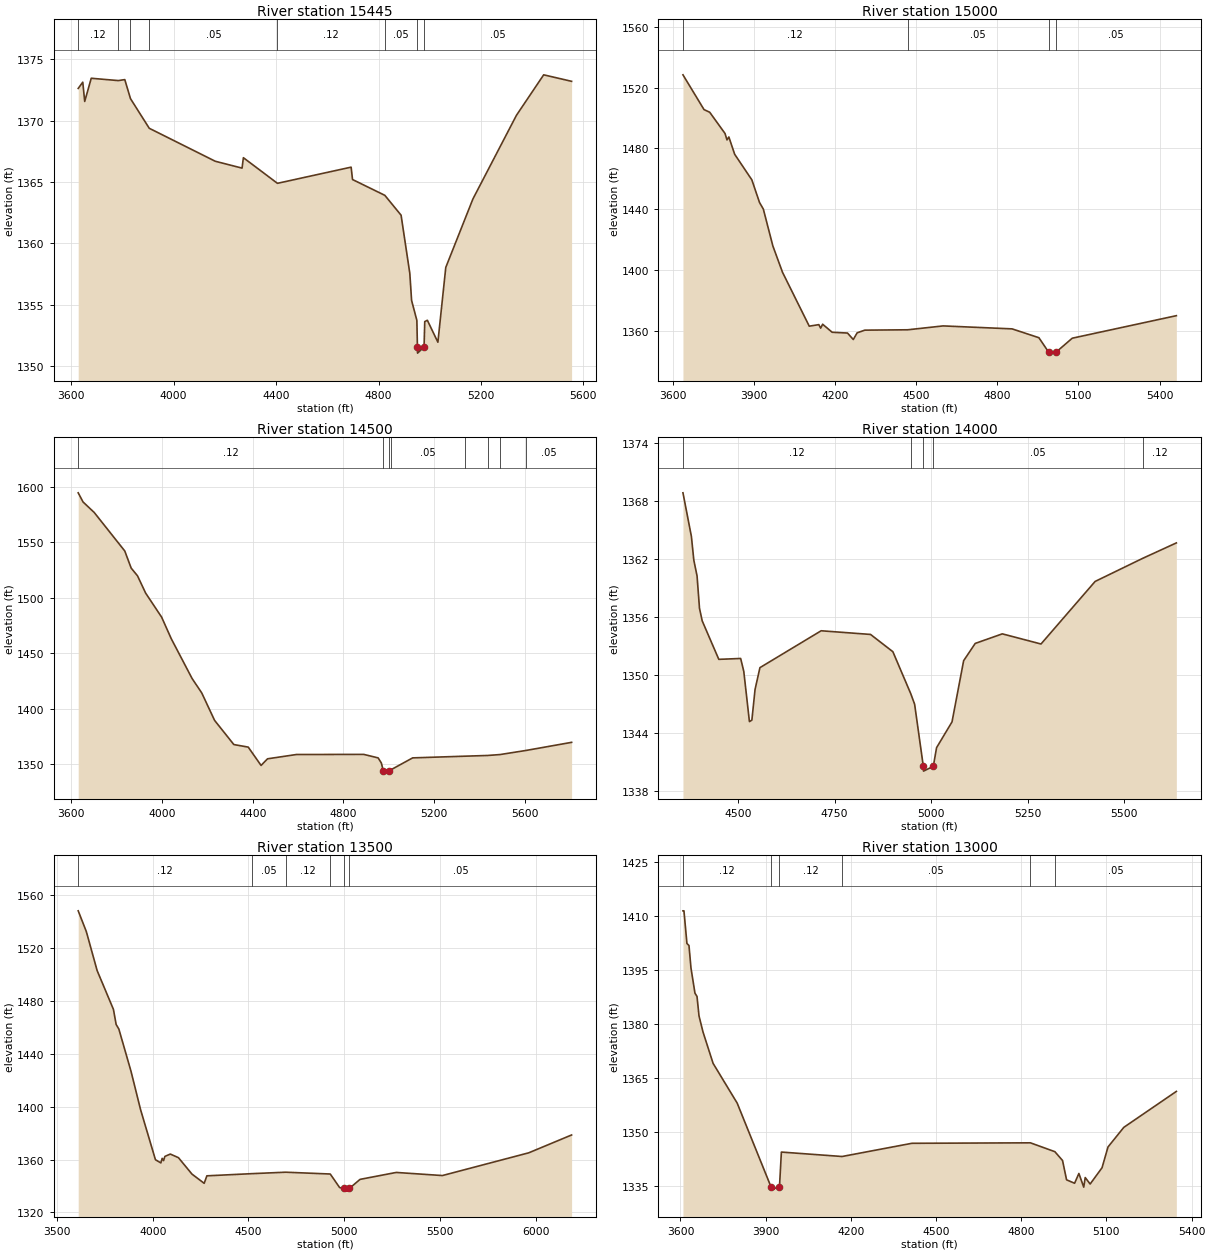
Type RM Length L Ch R = 1 ,15445   ,445,445,445
BEGIN DESCRIPTION:
Mapping XS 441cdf40
END DESCRIPTION:
XS GIS Cut Line= 4
      2745189.99     10283813.68      2744362.13     10284061.27
      2743727.68     10284208.27      2743456.87     10284517.77
#Sta/Elev= 30
  3627.2 1372.63    3645 1373.14  3652.6 1371.57  3678.1 1373.46  3783.6 1373.27
  3809.1 1373.35  3831.3  1371.8  3904.6 1369.38  4162.5 1366.69    4267 1366.13
  4272.2 1366.98  4405.2 1364.89  4692.9 1366.21  4698.4  1365.2  4824.6 1363.91
    4888 1362.29  4922.1 1357.54    4929 1355.34  4949.6 1353.71  4951.8 1351.54
  4952.3 1351.04  4977.7 1351.54  4980.4 1353.61  4990.6 1353.72  5031.7 1351.93
  5062.5 1358.03  5168.6 1363.62  5338.5 1370.44  5444.8 1373.74  5553.8 1373.21
#Mann= 8 ,-1 , 0
  3627.2     .12       0  3783.6     .05       0  3831.3     .12       0
  3904.6     .05       0  4405.2     .12       0  4824.6     .05       0
  4951.8     .05       0  4977.7     .05       0
Bank Sta=4951.8,4977.7
XS Rating Curve= 0 ,0
Exp/Cntr=0.3,0.1

Type RM Length L Ch R = 1 ,15000   ,500,500,500
BEGIN DESCRIPTION:
COLD CREEK 30.0
END DESCRIPTION:
XS GIS Cut Line= 3
      2744605.67     10282803.13      2743672.32     10283794.78
       2743455.7     10284203.08
#Sta/Elev= 30
  3638.2 1528.44  3716.1 1505.54  3737.1  1503.8  3793.7 1489.82    3801  1485.6
  3807.9 1487.51  3829.4 1476.12  3892.9 1459.28  3921.2 1444.39  3935.4    1440
  3970.5 1415.79  4006.2 1398.43  4105.1 1362.93  4140.5 1363.94  4147.3 1361.63
  4154.6 1364.21  4189.8 1358.91  4246.5  1358.4  4267.9 1354.15  4282.1 1358.54
  4310.4 1360.31  4469.1 1360.55  4600.1  1363.1    4855 1361.15  4954.1 1355.33
  4990.7 1345.68  4991.2 1345.18  5016.6 1345.68  5077.4 1355.01  5462.2 1369.84
#Mann= 4 ,-1 , 0
  3638.2     .12       0  4469.1     .05       0  4990.7     .05       0
  5016.6     .05       0
Bank Sta=4990.7,5016.6
XS Rating Curve= 0 ,0
Exp/Cntr=0.3,0.1

Type RM Length L Ch R = 1 ,14500   ,500,500,500
BEGIN DESCRIPTION:
COLD CREEK 29.0
END DESCRIPTION:
XS GIS Cut Line= 3
      2744255.67     10282453.13      2743314.35     10283448.26
      2743355.68      10284253.1
#Sta/Elev= 30
  3630.2 1594.41  3651.4 1586.22  3700.8 1576.71  3835.5 1542.04  3863.8 1526.61
  3891.7 1519.67  3927.3 1504.21  3998.1 1482.42  4040.6 1462.99  4132.4 1427.18
  4174.9 1414.24  4231.5  1389.5  4316.5  1367.7    4380  1365.4  4436.6  1348.9
  4464.9 1354.86  4592.4 1358.73  4889.3 1358.84  4952.8 1355.69    4967 1351.06
  4975.5 1344.27    4976 1343.77  5001.4 1344.27  5011.1 1345.19    5105  1355.7
  5336.8 1357.23  5435.3 1357.87    5490 1358.68  5604.9 1362.39  5805.9 1369.69
#Mann= 8 ,-1 , 0
  3630.2     .12       0  4975.5     .07       0  5001.4     .12       0
  5011.1     .05       0  5336.8     .12       0  5435.3     .05       0
    5490     .12       0  5604.9     .05       0
Bank Sta=4975.5,5001.4
XS Rating Curve= 0 ,0
Exp/Cntr=0.3,0.1

Type RM Length L Ch R = 1 ,14000   ,500,500,500
BEGIN DESCRIPTION:
COLD CREEK 28.0
END DESCRIPTION:
XS GIS Cut Line= 3
      2743255.68     10282703.12      2742872.78     10283218.94
      2742905.68     10283853.09
#Sta/Elev= 30
  4357.6 1368.87  4379.5 1364.34  4385.7  1361.9  4394.1 1360.26  4400.4 1356.91
  4407.4 1355.61  4450.4 1351.62    4507 1351.71  4515.1 1350.37  4529.7 1345.17
    4536 1345.32  4544.3 1348.51  4556.9 1350.76  4715.4 1354.58  4843.3  1354.2
  4901.1 1352.41  4947.4 1348.06  4957.4 1346.97  4979.9 1340.54  4980.4 1340.04
  5005.8 1340.54  5014.2 1342.47  5054.2 1345.14  5084.3 1351.48  5114.3 1353.27
  5184.4 1354.26  5284.6 1353.21  5424.7 1359.69  5547.7 1362.08    5635 1363.68
#Mann= 5 ,-1 , 0
  4357.6     .12       0  4947.4     .05       0  4979.9     .03       0
  5005.8     .05       0  5547.7     .12       0
Bank Sta=4979.9,5005.8
XS Rating Curve= 0 ,0
Exp/Cntr=0.3,0.1

Type RM Length L Ch R = 1 ,13500   ,500,500,500
BEGIN DESCRIPTION:
COLD CREEK 27.0
END DESCRIPTION:
XS GIS Cut Line= 3
      2743355.71     10282003.08      2742416.18     10283027.21
      2741405.72     10283653.09
#Sta/Elev= 30
  3610.2 1547.96  3652.5 1532.34  3709.2 1502.77  3794.3 1473.47  3808.5 1462.04
  3822.7 1458.57  3886.2 1426.66  3935.9 1397.79  4013.8 1359.84  4042.2 1357.43
    4049 1360.86  4056.3 1359.16  4063.1 1362.34  4091.5 1364.11    4134 1361.39
  4204.9 1348.95  4268.5    1342  4282.6 1347.66    4519 1349.31  4694.4  1350.4
  4927.4 1349.03  4976.3  1338.8  4997.8 1338.11  4998.3 1337.61  5026.8 1338.11
  5083.2 1344.99  5272.3 1350.22  5513.4 1347.87  5964.8 1365.06  6188.6 1378.54
#Mann= 6 ,-1 , 0
  3610.2     .12       0    4519     .05       0  4694.4     .12       0
  4927.4     .05       0  4997.8     .05       0  5026.8     .05       0
Bank Sta=4997.8,5026.8
XS Rating Curve= 0 ,0
Exp/Cntr=0.3,0.1

Type RM Length L Ch R = 1 ,13000   ,500,500,500
BEGIN DESCRIPTION:
COLD CREEK 26.0
END DESCRIPTION:
XS GIS Cut Line= 3
      2742905.68     10281903.11      2741936.49     10282901.16
      2741605.64     10283003.12
#Sta/Elev= 30
  3608.8 1411.42  3612.3 1411.42  3622.8 1402.35    3630 1401.77    3637 1395.53
  3651.1 1388.53  3658.3 1387.61  3665.3 1382.22  3679.4 1377.74  3714.9 1369.02
  3799.8 1357.96  3919.5 1334.56    3920 1334.06  3948.6 1334.56  3955.4 1344.36
  4169.1 1343.13  4415.1  1346.8  4832.3 1346.93  4918.4 1344.47  4945.5 1342.01
  4959.6 1336.65  4987.9 1335.69    5003 1338.41  5020.1 1334.61  5025.3 1337.28
  5042.7 1335.48  5084.6 1340.01  5105.5 1345.77  5161.2 1351.23  5346.2 1361.22
#Mann= 6 ,-1 , 0
  3608.8     .12       0  3919.5     .03       0  3948.6     .12       0
  4169.1     .05       0  4832.3     .12       0  4918.4     .05       0
Bank Sta=3919.5,3948.6
XS Rating Curve= 0 ,0
Exp/Cntr=0.3,0.1

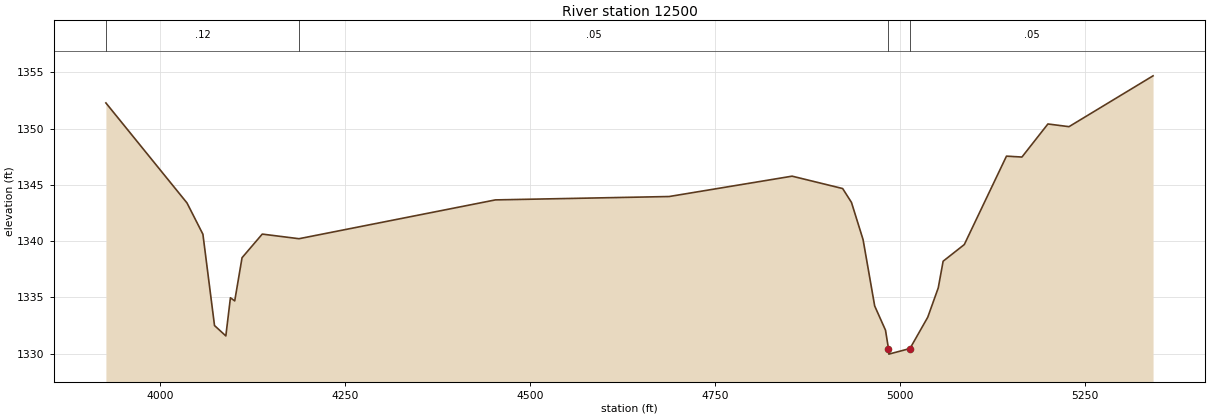
Type RM Length L Ch R = 1 ,12500   ,500,500,500
BEGIN DESCRIPTION:
COLD CREEK 25.0
END DESCRIPTION:
XS GIS Cut Line= 3
       2742605.7      10281953.1      2741678.54     10282493.98
      2741455.67     10282753.13
#Sta/Elev= 30
  3926.6 1352.29  4036.2  1343.4  4057.7 1340.62  4073.4  1332.5  4088.7 1331.58
  4094.9 1334.97  4100.7 1334.69  4110.6 1338.53  4137.9 1340.63  4187.6 1340.22
    4453 1343.67  4687.8 1343.97    4854 1345.78  4922.3 1344.68  4934.2 1343.45
  4949.9 1340.14  4965.6 1334.24  4980.2 1332.09  4984.2 1330.46  4984.7 1329.96
  5013.3 1330.46  5037.3 1333.24  5051.5 1335.85  5058.1 1338.22  5086.7  1339.7
  5143.7 1347.56  5164.6 1347.48  5199.7 1350.42  5228.2 1350.18  5341.8  1354.7
#Mann= 4 ,-1 , 0
  3926.6     .12       0  4187.6     .05       0  4984.2     .05       0
  5013.3     .05       0
Bank Sta=4984.2,5013.3
XS Rating Curve= 0 ,0
Exp/Cntr=0.3,0.1