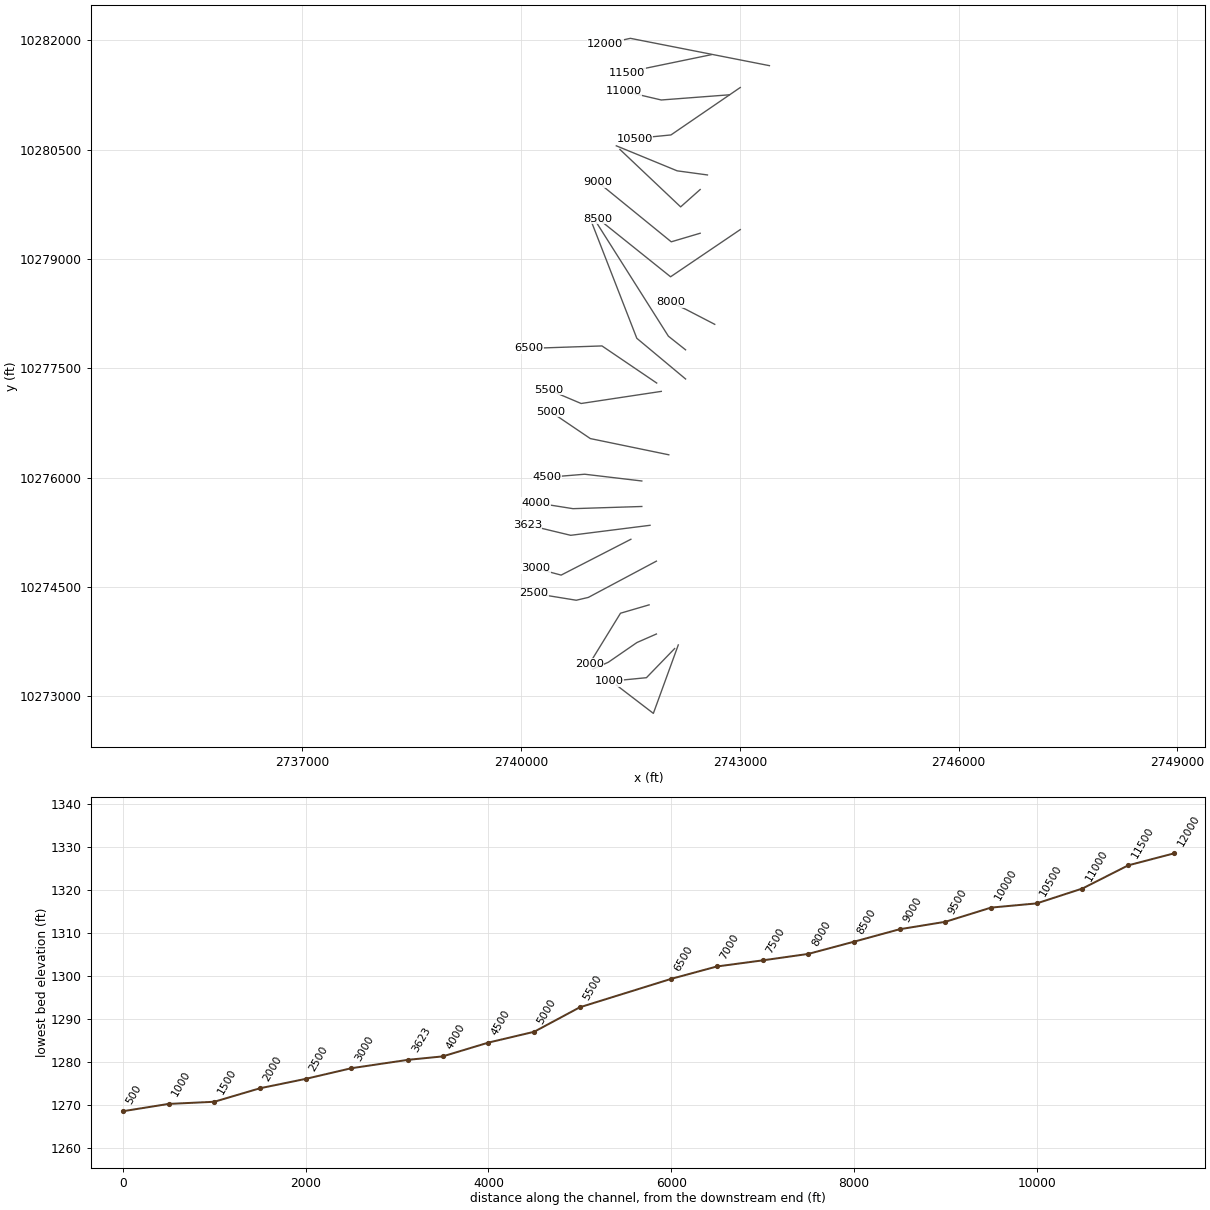
HEC-RAS study COLD CREEK.prj: COLD CREEK Base Level Engineering

--- COLD CREEK.g01 (geometry) --- (continued)

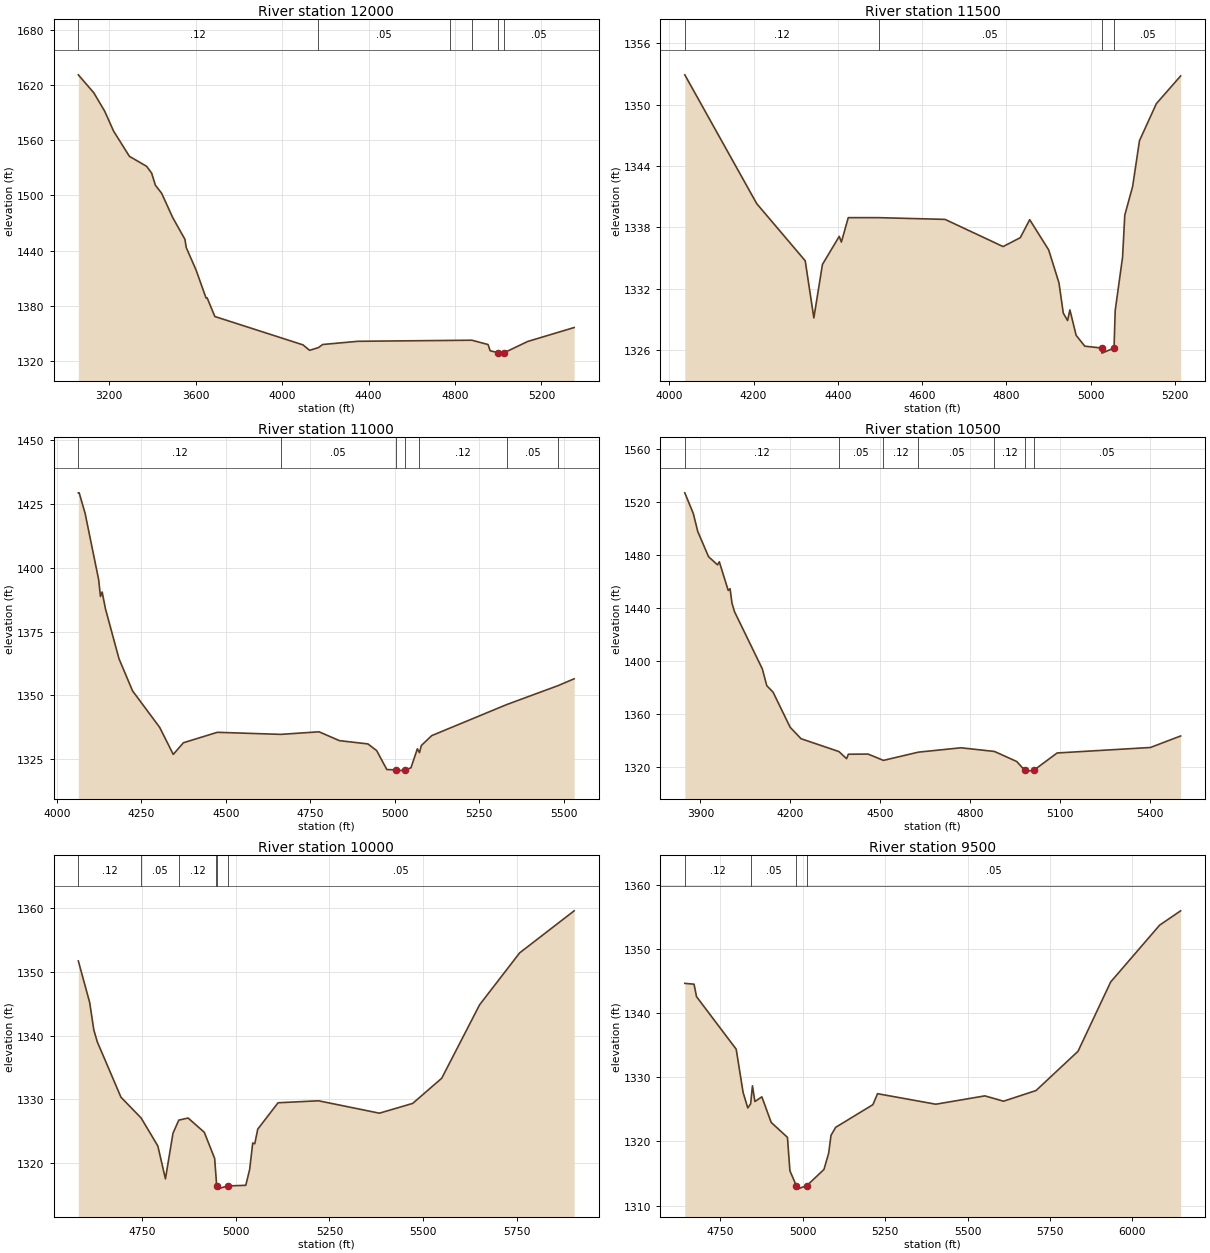
Type RM Length L Ch R = 1 ,12000   ,500,500,500
BEGIN DESCRIPTION:
COLD CREEK 24.0
END DESCRIPTION:
XS GIS Cut Line= 3
      2743405.73      10281653.1      2741498.84     10282028.08
      2741155.64      10281953.1
#Sta/Elev= 30
  3056.6 1631.14    3128 1611.66  3178.9 1591.47  3219.7 1569.97    3293 1542.51
  3372.6 1531.64  3395.8  1524.3  3413.3 1511.05  3442.1 1502.35  3493.5 1475.87
    3550 1452.24    3556 1443.29  3601.4 1418.93  3647.7 1388.37  3652.7 1388.62
  3688.5 1368.27  4096.2 1337.46  4126.8 1331.51  4167.2 1334.42  4187.9 1337.86
    4351 1341.33  4776.5 1342.28  4878.1  1342.5  4952.8 1337.81  4962.5 1331.06
  4998.9 1328.96  4999.4 1328.46  5028.1 1328.96  5135.8  1341.1  5351.3  1356.3
#Mann= 6 ,-1 , 0
  3056.6     .12       0  4167.2     .05       0  4776.5     .12       0
  4878.1     .05       0  4998.9     .05       0  5028.1     .05       0
Bank Sta=4998.9,5028.1
XS Rating Curve= 0 ,0
Exp/Cntr=0.3,0.1

Type RM Length L Ch R = 1 ,11500   ,500,500,500
BEGIN DESCRIPTION:
COLD CREEK 23.0
END DESCRIPTION:
XS GIS Cut Line= 3
      2742605.71     10281803.12      2741662.33     10281608.26
      2741455.66     10281553.11
#Sta/Elev= 30
  4036.7 1352.92  4207.5 1340.31  4322.6 1334.72  4343.1 1329.13  4363.5 1334.36
  4403.4 1337.11  4408.5 1336.55  4424.8 1338.94    4497 1338.94  4654.6 1338.77
  4792.4 1336.11  4833.2 1336.98  4855.6 1338.74  4900.7 1335.78  4925.1 1332.55
  4935.3  1329.6  4945.5 1328.87    4951 1329.91  4965.9 1327.42  4986.4 1326.36
  5026.6 1326.18  5027.1 1325.68  5055.8 1326.18  5058.6 1329.86  5076.1 1335.08
  5081.3 1339.18    5100    1342  5116.2 1346.47  5156.3  1350.1  5213.9 1352.81
#Mann= 4 ,-1 , 0
  4036.7     .12       0    4497     .05       0  5026.6     .05       0
  5055.8     .05       0
Bank Sta=5026.6,5055.8
XS Rating Curve= 0 ,0
Exp/Cntr=0.3,0.1

Type RM Length L Ch R = 1 ,11000   ,500,500,500
BEGIN DESCRIPTION:
COLD CREEK 22.0
END DESCRIPTION:
XS GIS Cut Line= 3
      2742855.64     10281253.11      2741922.25     10281182.03
      2741405.65     10281303.12
#Sta/Elev= 30
  4063.9 1429.41  4066.4 1429.41  4083.9  1421.4    4124 1395.39  4129.4 1388.76
  4134.4 1390.53  4144.1 1383.96  4184.2 1364.36  4224.3 1351.77  4304.6 1337.44
  4344.7 1326.85  4374.8 1331.43    4475 1335.52  4662.9 1334.71  4775.9 1335.72
  4836.1 1332.26  4920.6 1330.96  4946.4 1328.35  4976.5 1320.92  5002.4  1320.8
  5002.9  1320.3  5031.6  1320.8  5047.8  1321.6  5066.8 1329.06    5073 1327.55
  5078.6 1330.35  5109.3 1334.22  5330.8 1346.38    5483 1353.82  5530.6  1356.5
#Mann= 7 ,-1 , 0
  4063.9     .12       0  4662.9     .05       0  5002.4     .05       0
  5031.6     .05       0    5073     .12       0  5330.8     .05       0
    5483     .12       0
Bank Sta=5002.4,5031.6
XS Rating Curve= 0 ,0
Exp/Cntr=0.3,0.1

Type RM Length L Ch R = 1 ,10500   ,500,500,500
BEGIN DESCRIPTION:
COLD CREEK 21.0
END DESCRIPTION:
XS GIS Cut Line= 3
      2743005.67      10281353.1      2742055.07     10280702.19
      2741555.67     10280653.11
#Sta/Elev= 30
  3847.9 1527.14  3876.3  1511.5  3891.2 1497.89  3927.1 1478.88  3956.9 1472.74
    3963 1475.05  3992.8 1453.36  3998.9 1454.68  4005.4 1443.62  4013.8 1437.29
  4106.5  1394.1  4121.4 1381.41  4142.4 1376.51  4199.4 1349.96  4235.7 1341.33
    4362 1331.63  4387.5 1326.25  4393.5 1329.61  4459.2 1329.73  4510.4 1324.96
  4626.9 1331.17    4769 1334.48  4880.8 1331.71  4955.5 1324.07    4982 1317.34
  4982.5 1316.84  5011.2 1317.34  5089.8 1330.55  5401.3 1334.71  5501.8 1343.41
#Mann= 7 ,-1 , 0
  3847.9     .12       0    4362     .05       0  4510.4     .12       0
  4626.9     .05       0  4880.8     .12       0    4982     .05       0
  5011.2     .05       0
Bank Sta=4982,5011.2
XS Rating Curve= 0 ,0
Exp/Cntr=0.3,0.1

Type RM Length L Ch R = 1 ,10000   ,500,500,500
BEGIN DESCRIPTION:
COLD CREEK 20.0
END DESCRIPTION:
XS GIS Cut Line= 3
      2742555.72     10280153.11      2742140.06     10280209.73
      2741305.66     10280553.12
#Sta/Elev= 30
  4580.5 1351.74  4610.8  1345.2  4621.8 1340.89    4631 1339.03  4694.1 1330.32
    4748 1327.04  4792.5 1322.64  4812.7 1317.47  4832.8 1324.64  4848.3 1326.71
  4873.2 1327.04  4916.3  1324.8  4943.9 1320.69  4948.6 1316.99  4949.4 1316.36
  4949.9 1315.86  4978.6 1316.36  5026.9 1316.46  5037.2 1318.95  5045.4 1323.11
  5050.8 1322.99  5058.8 1325.29  5112.9 1329.44    5221 1329.75  5383.2  1327.8
  5471.9 1329.34  5549.2 1333.29  5650.4 1344.86    5757 1353.01  5902.3 1359.62
#Mann= 6 ,-1 , 0
  4580.5     .12       0    4748     .05       0  4848.3     .12       0
  4948.6     .05       0  4949.4     .03       0  4978.6     .05       0
Bank Sta=4949.4,4978.6
XS Rating Curve= 0 ,0
Exp/Cntr=0.3,0.1

Type RM Length L Ch R = 1 ,9500    ,500,500,500
BEGIN DESCRIPTION:
COLD CREEK 19.0
END DESCRIPTION:
XS GIS Cut Line= 3
      2742455.72     10279953.14      2742188.06     10279714.95
       2741355.7      10280503.1
#Sta/Elev= 30
  4641.7 1344.62  4669.8 1344.49  4677.3 1342.55  4797.7 1334.36  4818.6 1327.63
  4832.8 1325.21  4841.5 1325.85    4847 1328.66  4854.5 1326.21  4875.5 1326.94
  4903.9 1322.95  4953.2 1320.63  4960.7 1315.41  4980.5 1313.06    4981 1312.56
  5011.2 1313.06    5064 1315.63  5078.2 1318.14  5085.4 1320.95  5099.6 1322.19
  5212.5 1325.72  5226.6 1327.43  5403.4 1325.79  5552.3 1327.09  5608.9 1326.26
  5707.6 1327.92    5835 1334.04  5934.1 1344.84  6082.6 1353.69  6146.3 1355.92
#Mann= 4 ,-1 , 0
  4641.7     .12       0  4841.5     .05       0  4980.5     .03       0
  5011.2     .05       0
Bank Sta=4980.5,5011.2
XS Rating Curve= 0 ,0
Exp/Cntr=0.3,0.1

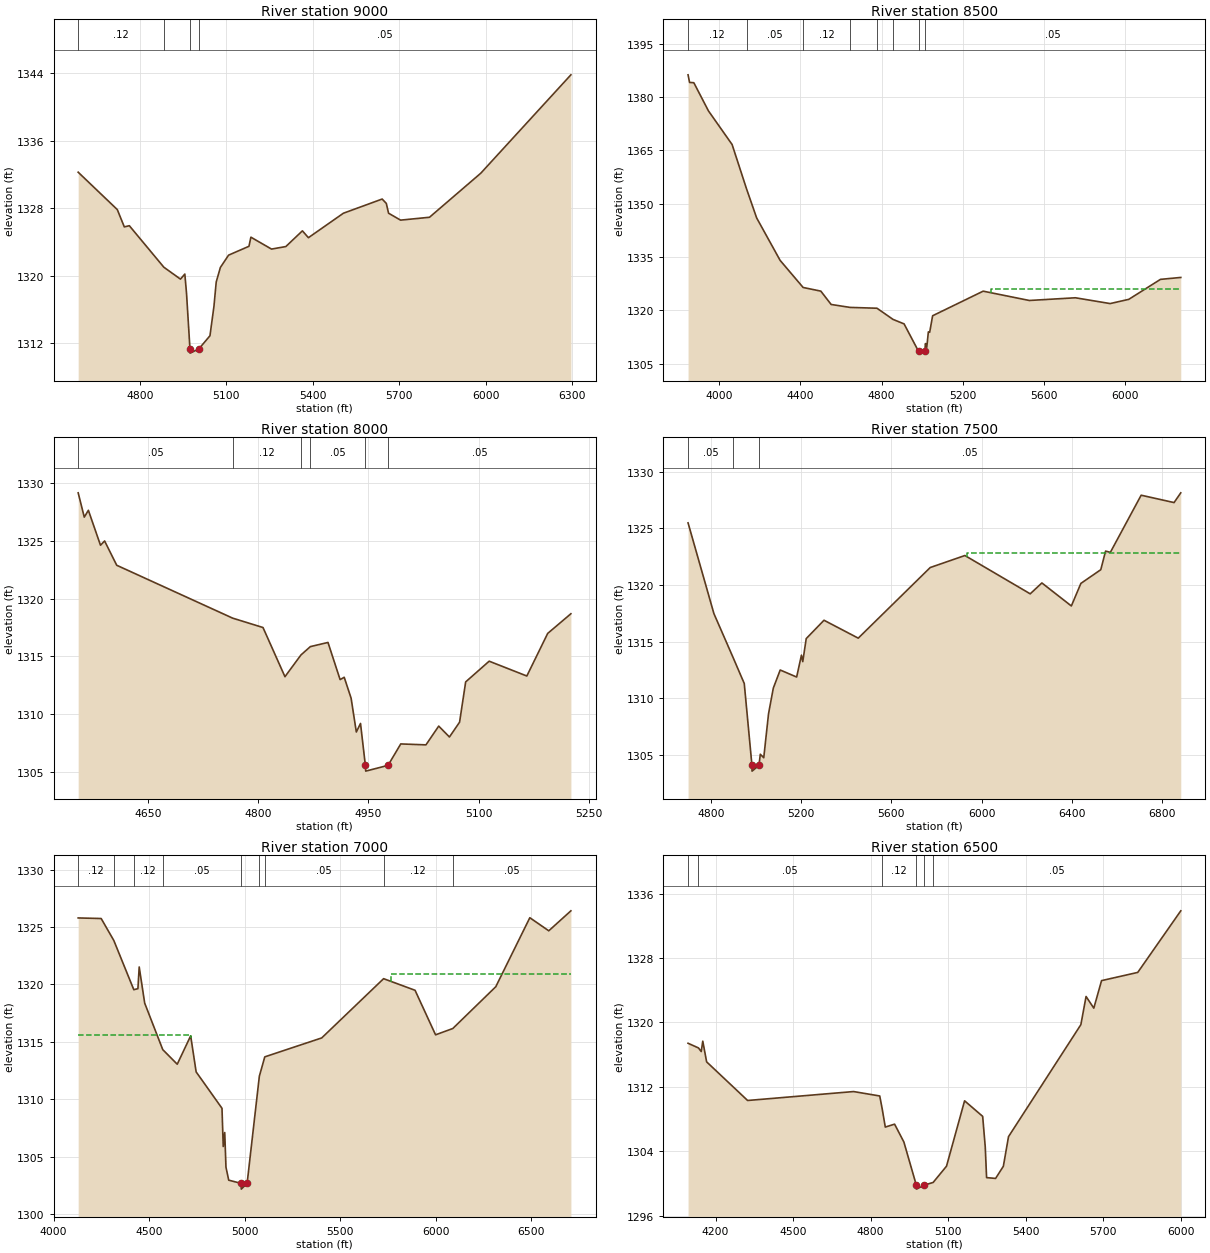
Type RM Length L Ch R = 1 ,9000    ,500,500,500
BEGIN DESCRIPTION:
COLD CREEK 18.0
END DESCRIPTION:
XS GIS Cut Line= 3
      2742455.66      10279353.1      2742059.33     10279235.52
       2741055.7      10280053.1
#Sta/Elev= 30
  4586.6 1332.27  4722.2 1327.84  4746.5 1325.79  4763.9 1325.93  4883.6 1321.01
  4941.2  1319.6  4956.3  1320.2  4962.1 1317.95  4974.1 1311.33  4974.6 1310.83
  5004.9 1311.33  5043.4 1312.89  5057.2 1316.37  5065.1 1319.26  5079.5 1320.98
  5107.9 1322.44  5178.6 1323.49  5185.3 1324.57  5256.8 1323.16  5306.4 1323.46
  5363.8 1325.32  5384.7 1324.51    5506 1327.41  5640.3 1329.09  5654.7 1328.57
  5662.5 1327.41  5704.2 1326.59  5804.4 1326.93  5982.1 1332.15  6294.5 1343.81
#Mann= 4 ,-1 , 0
  4586.6     .12       0  4883.6     .05       0  4974.1     .05       0
  5004.9     .05       0
Bank Sta=4974.1,5004.9
XS Rating Curve= 0 ,0
Exp/Cntr=0.3,0.1

Type RM Length L Ch R = 1 ,8500    ,500,500,500
BEGIN DESCRIPTION:
COLD CREEK 17.0
END DESCRIPTION:
XS GIS Cut Line= 3
      2743005.68     10279403.11      2742050.11     10278755.59
       2741055.7      10279553.1
#Sta/Elev= 30
  3845.7 1386.22  3853.2 1384.08  3874.2    1384  3946.1 1376.09  4062.8 1366.62
  4133.8 1354.18  4183.9 1345.96  4299.5 1334.03  4412.9  1326.4  4500.2 1325.37
  4551.1 1321.62  4644.7 1320.79  4777.1 1320.56  4856.3 1317.41  4910.6 1316.16
    4982 1308.43  4982.5 1307.93  5012.9 1308.43    5016 1310.62  5022.5 1309.57
  5030.4 1313.92  5036.9  1313.8  5051.3 1318.44  5300.5 1325.36  5528.2 1322.74
  5755.4  1323.5  5926.6 1321.87  6018.3 1323.06  6174.7 1328.68  6274.7 1329.22
#Mann= 8 ,-1 , 0
  3845.7     .12       0  4133.8     .05       0  4412.9     .12       0
  4644.7      .1       0  4777.1     .12       0  4856.3     .05       0
    4982     .05       0  5012.9     .05       0
#XS Ineff= 2 , 0
                         5338.56         1325.99
Permanent Ineff=
       F       F
Bank Sta=4982,5012.9
XS Rating Curve= 0 ,0
Exp/Cntr=0.3,0.1

Type RM Length L Ch R = 1 ,8000    ,500,500,500
BEGIN DESCRIPTION:
COLD CREEK 16.0
END DESCRIPTION:
XS GIS Cut Line= 3
      2742655.72     10278103.09      2742260.46     10278307.98
      2742055.68     10278403.11
#Sta/Elev= 30
  4554.8 1329.14  4563.1 1327.04  4568.7 1327.63  4585.2 1324.61  4590.8 1324.98
  4607.3 1322.88  4765.2 1318.31  4806.5  1317.5  4836.4 1313.25  4858.2 1315.13
    4871 1315.85    4895 1316.21  4911.5    1313  4917.1  1313.2  4926.5 1311.39
  4933.6 1308.47  4939.3 1309.21  4945.9 1305.59  4946.4 1305.09  4976.8 1305.59
  4994.1 1307.44  5028.4 1307.36  5045.8 1308.98  5060.4 1308.04  5074.2 1309.32
  5082.5  1312.8  5114.5 1314.59  5165.8 1313.31  5194.2 1316.99  5225.8 1318.69
#Mann= 6 ,-1 , 0
  4554.8     .05       0  4765.2     .12       0  4858.2      .1       0
    4871     .05       0  4945.9     .03       0  4976.8     .05       0
Bank Sta=4945.9,4976.8
XS Rating Curve= 0 ,0
Exp/Cntr=0.3,0.1

Type RM Length L Ch R = 1 ,7500    ,500,500,500
BEGIN DESCRIPTION:
COLD CREEK 15.0
END DESCRIPTION:
XS GIS Cut Line= 3
      2742255.66     10277753.13      2742019.96     10277940.35
      2741013.81     10279531.76
#Sta/Elev= 30
    4699 1325.49  4813.5 1317.49  4898.4 1313.62  4948.1 1311.32  4982.2 1304.09
  4982.7 1303.59  5013.2 1304.09  5019.2 1305.08  5034.5 1304.77  5055.6 1308.64
  5076.8 1310.91  5107.4 1312.51  5180.3 1311.89  5201.5 1313.82  5207.4 1313.25
  5222.7 1315.28  5301.5  1316.9  5453.3 1315.32  5772.3 1321.55  5926.1 1322.61
  6215.5 1319.23  6267.2 1320.19  6397.8 1318.16  6440.1 1320.15  6528.3 1321.36
  6549.5    1323  6570.7 1322.89  6707.2 1327.93    6853 1327.28  6882.8 1328.14
#Mann= 3 ,-1 , 0
    4699     .05       0  4898.4     .07       0  5013.2     .05       0
#XS Ineff= 2 , 0
                         5934.17         1322.85
Permanent Ineff=
       F       F
Bank Sta=4982.2,5013.2
XS Rating Curve= 0 ,0
Exp/Cntr=0.3,0.1

Type RM Length L Ch R = 1 ,7000    ,500,500,500
BEGIN DESCRIPTION:
COLD CREEK 14.0
END DESCRIPTION:
XS GIS Cut Line= 3
      2742255.69      10277353.1      2741586.87     10277911.53
      2740967.73     10279503.47
#Sta/Elev= 30
  4128.7 1325.79  4249.1 1325.74  4315.2 1323.83  4419.9 1319.54  4441.4 1319.63
  4448.2 1321.52  4476.9 1318.37  4571.5 1314.32  4647.3 1313.05  4717.6 1315.52
  4746.3 1312.38  4881.6 1309.21  4888.1 1305.88  4895.9  1307.1  4902.4 1304.08
  4916.8 1302.95    4982 1302.67  4982.5 1302.17  5013.1 1302.67  5077.2 1312.01
  5105.6 1313.69  5403.7 1315.34  5727.6  1320.5  5892.3 1319.49  5999.6 1315.61
  6089.9 1316.16  6314.9  1319.8  6493.1 1325.81  6592.3 1324.67  6708.1 1326.41
#Mann= 9 ,-1 , 0
  4128.7     .12       0  4315.2     .05       0  4419.9     .12       0
  4571.5     .05       0    4982       0       0  5077.2     .12       0
  5105.6     .05       0  5727.6     .12       0  6089.9     .05       0
#XS Ineff= 2 , 0
         4719.44  1315.6 5768.02          1320.9
Permanent Ineff=
       F       F
Bank Sta=4982,5013.1
XS Rating Curve= 0 ,0
Exp/Cntr=0.3,0.1

Type RM Length L Ch R = 1 ,6500    ,1000,1000,1000
BEGIN DESCRIPTION:
COLD CREEK 13.0
END DESCRIPTION:
XS GIS Cut Line= 3
      2741859.71     10277297.36      2741109.48     10277806.55
      2740109.16     10277772.66
#Sta/Elev= 30
  4093.3 1317.41  4133.5 1316.83  4144.3 1316.38  4150.3 1317.67  4165.2  1315.1
  4323.9  1310.3  4734.2 1311.41  4835.4 1310.86  4844.6 1309.32  4856.9    1307
  4892.9 1307.36  4928.8 1305.15    4977 1299.79  4977.5 1299.29  5008.1 1299.79
  5042.2 1300.12  5093.9 1302.14  5163.9 1310.26  5233.9 1308.33  5243.9 1304.54
  5249.1 1300.72    5284 1300.62    5314 1302.13    5334 1305.81  5614.1 1319.72
  5634.2 1323.22  5664.2 1321.77  5694.2 1325.19  5834.3 1326.21  6000.9 1333.86
#Mann= 6 ,-1 , 0
  4093.3     .12       0  4133.5     .05       0  4844.6     .12       0
    4977     .07       0  5008.1     .12       0  5042.2     .05       0
Bank Sta=4977,5008.1
XS Rating Curve= 0 ,0
Exp/Cntr=0.3,0.1

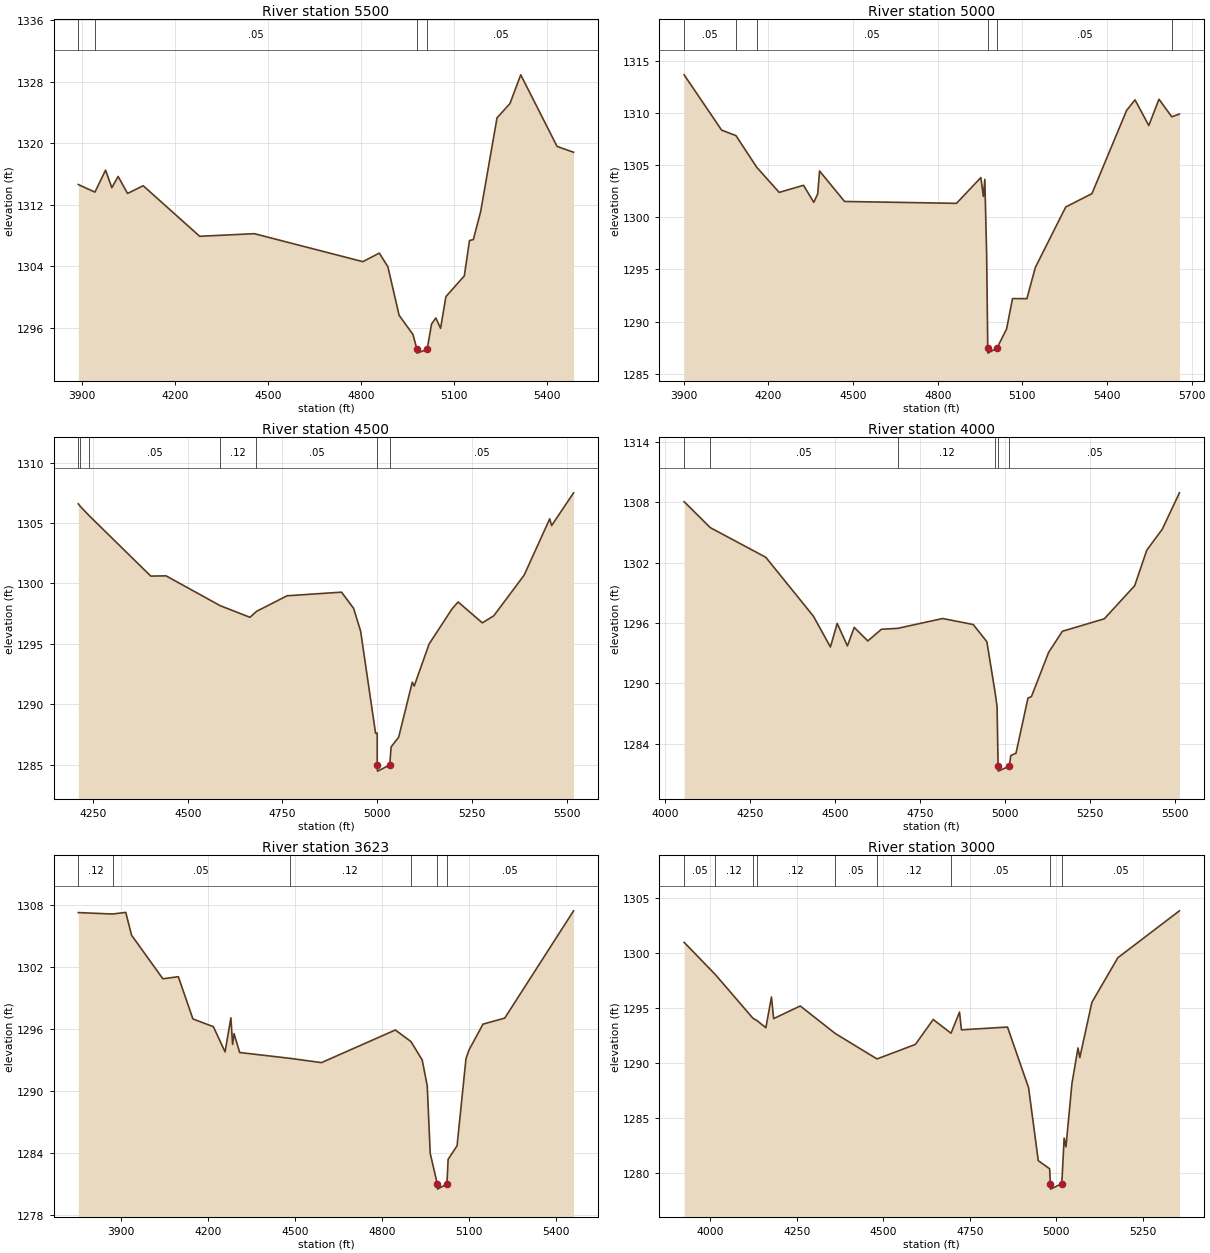
Type RM Length L Ch R = 1 ,5500    ,500,500,500
BEGIN DESCRIPTION:
COLD CREEK 11.0
END DESCRIPTION:
XS GIS Cut Line= 3
      2741922.62     10277182.86      2740823.11     10277016.61
      2740376.74     10277205.77
#Sta/Elev= 30
    3888 1314.63  3941.6 1313.64  3975.9  1316.5  3996.1 1314.21  4016.4 1315.68
  4046.7 1313.47  4097.3 1314.47  4279.3 1307.89  4455.6 1308.23  4805.2 1304.59
  4858.5  1305.7  4886.2 1303.92  4922.3 1297.61  4967.1  1295.1  4979.7 1293.18
  4980.3 1292.68  5012.7 1293.18  5026.9 1296.46  5040.7 1297.26    5056 1295.91
  5073.2 1300.04  5132.5 1302.73  5149.3 1307.34  5161.6 1307.46  5185.3 1311.12
    5238 1323.31  5279.6 1325.16  5314.5 1328.91  5431.6 1319.59  5484.8 1318.83
#Mann= 4 ,-1 , 0
    3888     .12       0  3941.6     .05       0  4979.7     .05       0
  5012.7     .05       0
Bank Sta=4979.7,5012.7
XS Rating Curve= 0 ,0
Exp/Cntr=0.3,0.1

Type RM Length L Ch R = 1 ,5000    ,500,500,500
BEGIN DESCRIPTION:
COLD CREEK 10.0
END DESCRIPTION:
XS GIS Cut Line= 3
      2742025.74     10276312.57      2740949.61     10276535.09
      2740405.71     10276903.09
#Sta/Elev= 30
  3901.1 1313.66  4033.9 1308.36  4084.8 1307.83  4158.6 1304.79  4238.1 1302.39
  4324.2 1303.07  4360.7 1301.44  4374.5 1302.25  4381.1 1304.44  4469.8 1301.52
  4866.5 1301.34  4952.9 1303.81  4961.8    1302  4966.9 1303.64  4973.4 1296.43
  4977.3 1287.48  4977.9 1286.98  5010.3 1287.48    5044 1289.29  5065.1 1292.21
    5116  1292.2  5145.9 1295.19  5253.7 1300.99  5346.6 1302.27  5469.5 1310.25
  5499.4 1311.26  5548.1  1308.8  5584.3 1311.32  5629.6 1309.64  5656.7  1309.9
#Mann= 6 ,-1 , 0
  3901.1     .05       0  4084.8     .12       0  4158.6     .05       0
  4977.3     .03       0  5010.3     .05       0  5629.6     .12       0
Bank Sta=4977.3,5010.3
XS Rating Curve= 0 ,0
Exp/Cntr=0.3,0.1

Type RM Length L Ch R = 1 ,4500    ,500,500,500
BEGIN DESCRIPTION:
COLD CREEK 9.0
END DESCRIPTION:
XS GIS Cut Line= 3
      2741655.68     10275953.11      2740872.24      10276045.8
       2740355.7     10276003.11
#Sta/Elev= 30
  4211.1 1306.59  4216.4 1306.38  4239.8 1305.61  4402.4 1300.61  4442.7 1300.63
  4585.7 1298.16  4664.2  1297.2  4681.4 1297.69  4762.1 1298.98  4905.9 1299.28
  4937.8 1297.94  4956.3 1296.05  4995.7 1287.61    5000 1287.61  5000.1 1284.97
  5000.7 1284.47  5033.1 1284.97  5036.7 1286.47  5056.7 1287.28  5092.6 1291.83
  5097.7 1291.51    5137 1294.99  5197.2 1297.88  5213.5 1298.47  5277.5 1296.74
  5307.6 1297.32  5387.9 1300.69  5455.4 1305.35  5460.4 1304.79  5518.3  1307.5
#Mann= 7 ,-1 , 0
  4211.1     .05       0  4216.4     .12       0  4239.8     .05       0
  4585.7     .12       0  4681.4     .05       0  5000.1     .05       0
  5033.1     .05       0
Bank Sta=5000.1,5033.1
XS Rating Curve= 0 ,0
Exp/Cntr=0.3,0.1

Type RM Length L Ch R = 1 ,4000    ,377,377,377
BEGIN DESCRIPTION:
COLD CREEK 8.0
END DESCRIPTION:
XS GIS Cut Line= 3
      2741655.65     10275603.11      2740711.63     10275573.17
       2740205.7     10275653.11
#Sta/Elev= 30
  4055.5 1308.06  4132.3 1305.48  4295.6 1302.53  4435.7 1296.67  4485.7 1293.61
  4505.7 1295.95  4535.7 1293.71  4555.7 1295.56  4595.7 1294.21  4635.8 1295.37
  4683.4 1295.46  4815.9 1296.44  4905.9 1295.84  4945.9 1294.13  4970.6 1288.98
  4975.9 1287.67  4978.9 1281.76  4979.5 1281.26  5012.1 1281.76  5016.1 1282.81
  5031.5 1283.04  5066.8 1288.53  5076.9 1288.67  5127.5 1293.07    5168 1295.17
  5291.2 1296.41  5380.6  1299.7  5416.1 1303.23  5461.6 1305.31  5512.2 1308.94
#Mann= 6 ,-1 , 0
  4055.5     .12       0  4132.3     .05       0  4683.4     .12       0
  4970.6     .05       0  4978.9     .05       0  5012.1     .05       0
Bank Sta=4978.9,5012.1
XS Rating Curve= 0 ,0
Exp/Cntr=0.3,0.1

Type RM Length L Ch R = 1 ,3623    ,623,623,623
BEGIN DESCRIPTION:
Mapping XS ad5c7d07
END DESCRIPTION:
XS GIS Cut Line= 3
      2741768.07     10275344.94       2740680.2     10275207.53
      2740084.78     10275350.66
#Sta/Elev= 30
  3752.5 1307.25  3870.8 1307.11  3916.2 1307.27  3936.3 1305.06  4044.3 1300.84
  4097.6 1301.04    4148 1296.95  4218.6  1296.2  4258.9 1293.76    4279 1297.06
  4284.9 1294.48    4290 1295.53  4309.3  1293.7  4481.6 1293.14  4591.5 1292.72
  4846.4 1295.88  4900.3 1294.76  4939.1 1292.98  4956.5 1290.47  4966.8 1283.93
  4991.3 1280.97  4991.9 1280.47  5024.5 1280.97  5028.5 1283.35  5059.4 1284.67
  5090.2 1293.11  5100.5 1293.94  5148.9 1296.45  5223.9 1297.03  5461.4 1307.42
#Mann= 6 ,-1 , 0
  3752.5     .12       0  3870.8     .05       0  4481.6     .12       0
  4900.3     .05       0  4991.3     .03       0  5024.5     .05       0
Bank Sta=4991.3,5024.5
XS Rating Curve= 0 ,0
Exp/Cntr=0.3,0.1

Type RM Length L Ch R = 1 ,3000    ,500,500,500
BEGIN DESCRIPTION:
COLD CREEK 6.0
END DESCRIPTION:
XS GIS Cut Line= 3
       2741505.7     10275153.12      2740549.26     10274661.47
      2740205.68     10274753.11
#Sta/Elev= 30
  3924.6 1300.97    4015 1298.03  4123.7 1294.05  4134.7 1293.86  4160.7  1293.2
  4176.9    1296  4183.2 1294.03    4260 1295.18  4361.5 1292.67  4481.8 1290.36
  4592.7 1291.68  4644.2 1293.95  4695.7  1292.7  4720.2 1294.62  4725.8 1293.01
  4858.9 1293.26  4919.8 1287.74  4947.8  1281.1  4980.7 1280.36  4982.6 1279.01
  4983.2 1278.51  5015.8 1279.01  5022.5 1283.16  5027.7 1282.35  5045.1 1288.13
  5062.6 1291.36  5067.8 1290.48  5102.7 1295.51  5177.7 1299.57  5355.6 1303.84
#Mann= 9 ,-1 , 0
  3924.6     .05       0    4015     .12       0  4123.7     .05       0
  4134.7     .12       0  4361.5     .05       0  4481.8     .12       0
  4695.7     .05       0  4982.6     .05       0  5015.8     .05       0
Bank Sta=4982.6,5015.8
XS Rating Curve= 0 ,0
Exp/Cntr=0.3,0.1

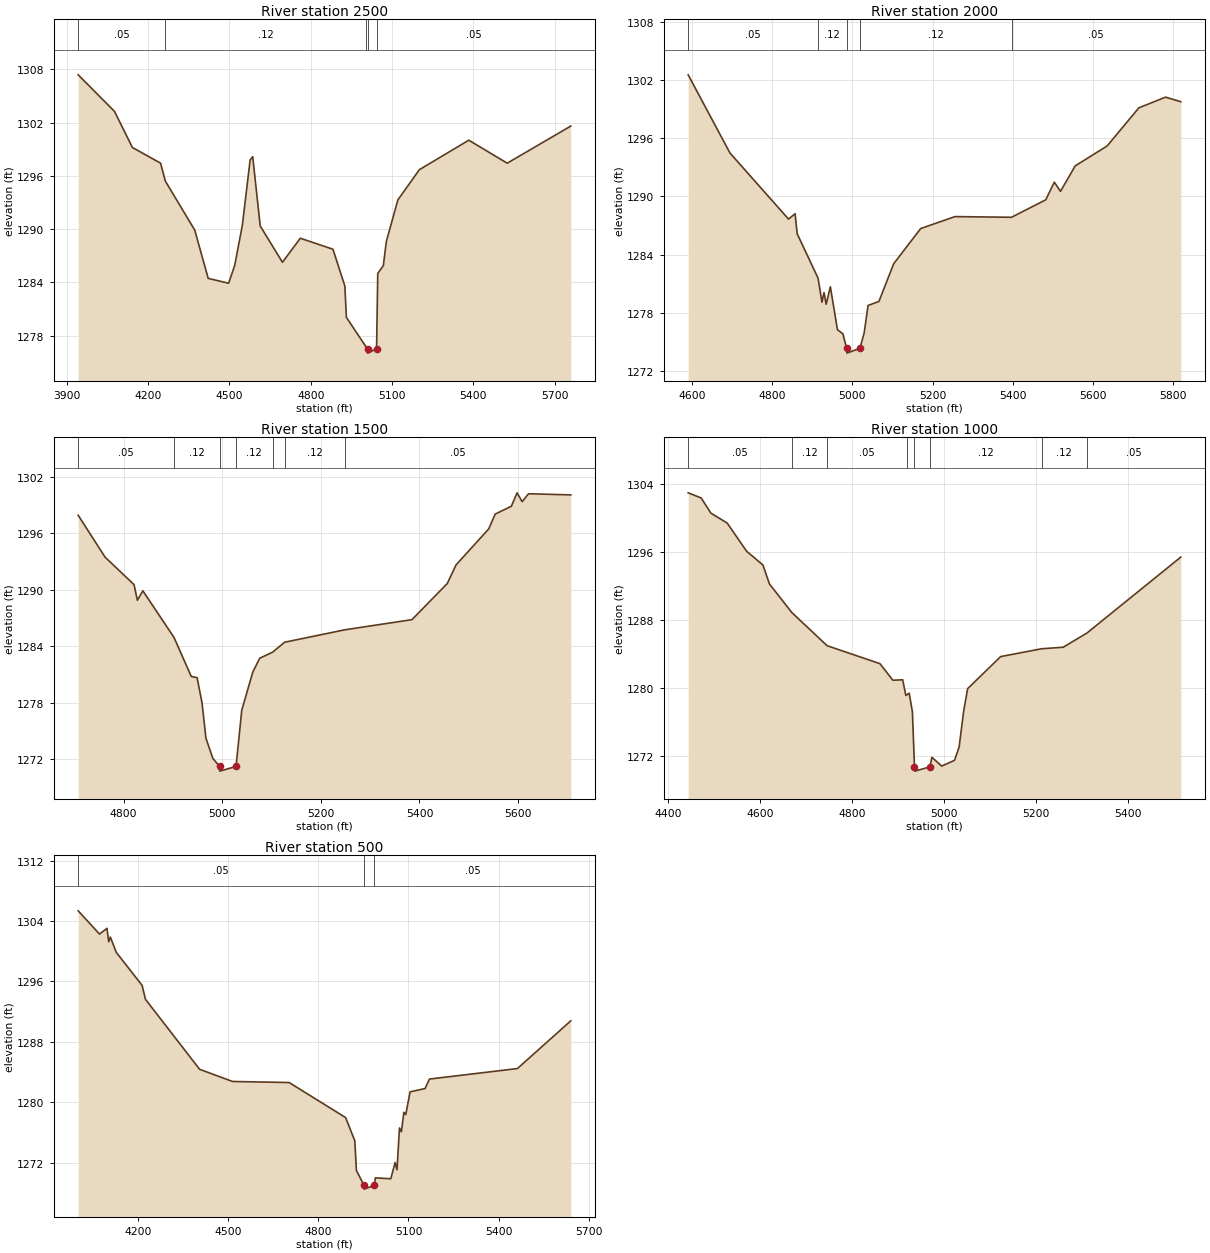
Type RM Length L Ch R = 1 ,2500    ,500,500,500
BEGIN DESCRIPTION:
COLD CREEK 5.0
END DESCRIPTION:
XS GIS Cut Line= 4
      2741855.67      10274853.1      2740921.92      10274355.2
      2740756.35      10274316.5      2740174.12      10274411.1
#Sta/Elev= 30
  3941.8 1307.37    4076 1303.25  4141.9 1299.19    4246 1297.42  4263.6  1295.4
  4372.1 1289.88  4421.7 1284.45  4497.1  1283.9  4519.8 1285.94  4547.8 1290.44
  4576.4 1297.78    4586 1298.15  4613.7 1290.35  4695.8 1286.26  4761.7 1288.97
  4882.1 1287.73  4926.1 1283.58  4931.7 1280.06  5004.2 1276.74  5009.9 1276.53
  5010.5 1276.03  5043.1 1276.53  5047.5    1285    5068 1285.88  5079.3 1288.62
  5121.8 1293.29  5201.1 1296.69  5383.5 1300.01  5525.3 1297.42  5759.9  1301.6
#Mann= 5 ,-1 , 0
  3941.8     .05       0  4263.6     .12       0  5004.2     .05       0
  5009.9     .07       0  5043.1     .05       0
Bank Sta=5009.9,5043.1
XS Rating Curve= 0 ,0
Exp/Cntr=0.3,0.1

Type RM Length L Ch R = 1 ,2000    ,500,500,500
BEGIN DESCRIPTION:
COLD CREEK 4.0
END DESCRIPTION:
XS GIS Cut Line= 3
      2741755.69     10274253.11      2741363.24     10274138.29
      2740935.06     10273440.84
#Sta/Elev= 30
  4591.1 1302.53  4695.3 1294.47  4841.2 1287.66  4857.5 1288.22  4862.7 1286.15
  4914.8 1281.57  4924.4  1279.1  4929.6 1280.09  4934.9 1278.89  4945.4 1280.69
    4963 1276.27  4976.6 1275.84  4985.9 1274.35  4986.6 1273.85  5019.2 1274.35
  5029.7 1275.96  5039.3 1278.76  5066.4 1279.18  5103.1 1283.06  5170.4 1286.69
  5255.9 1287.92  5396.7 1287.85    5482 1289.65  5503.3 1291.47  5518.7 1290.52
  5555.4 1293.15  5634.7 1295.19    5714 1299.13  5780.5 1300.23  5818.4 1299.76
#Mann= 5 ,-1 , 0
  4591.1     .05       0  4914.8     .12       0  4985.9     .07       0
  5019.2     .12       0  5396.7     .05       0
Bank Sta=4985.9,5019.2
XS Rating Curve= 0 ,0
Exp/Cntr=0.3,0.1

Type RM Length L Ch R = 1 ,1500    ,500,500,500
BEGIN DESCRIPTION:
COLD CREEK 3.0
END DESCRIPTION:
XS GIS Cut Line= 4
      2741855.69     10273853.11      2741588.39     10273735.84
      2741195.95     10273465.33      2740985.58     10273371.94
#Sta/Elev= 30
  4708.1 1297.91  4762.7 1293.45  4821.4 1290.53  4828.2 1288.87  4839.2 1289.88
  4902.4 1284.92  4937.4 1280.77  4949.2 1280.65  4959.3 1277.94  4967.1 1274.22
  4981.1 1272.07  4994.7 1271.21  4995.3 1270.71  5028.2 1271.21  5039.7 1277.17
  5062.2 1281.25  5076.2 1282.71  5102.4 1283.36  5126.6 1284.41  5248.6 1285.73
  5384.8 1286.81  5456.4 1290.65  5474.2 1292.63  5540.4 1296.45  5553.5 1298.03
  5586.3 1298.86  5597.9 1300.29  5608.2 1299.35  5621.1 1300.19  5706.8 1300.07
#Mann= 7 ,-1 , 0
  4708.1     .05       0  4902.4     .12       0  4994.7     .07       0
  5028.2     .12       0  5102.4     .05       0  5126.6     .12       0
  5248.6     .05       0
Bank Sta=4994.7,5028.2
XS Rating Curve= 0 ,0
Exp/Cntr=0.3,0.1

Type RM Length L Ch R = 1 ,1000    ,500,500,500
BEGIN DESCRIPTION:
COLD CREEK 2.0
END DESCRIPTION:
XS GIS Cut Line= 3
      2742105.67      10273653.1      2741719.02     10273253.55
      2741205.69     10273203.11
#Sta/Elev= 30
    4444 1302.94  4472.2 1302.34  4493.5 1300.55  4528.8 1299.39  4571.2 1296.07
  4606.7 1294.45  4620.8 1292.23  4669.4 1288.87  4746.3 1284.96  4861.3 1282.85
  4889.4  1280.9  4910.7 1280.95  4917.7  1279.1  4920.7 1279.22  4924.9 1279.38
  4931.9 1277.18  4936.4 1270.71    4937 1270.21    4970 1270.71  4974.3 1271.84
  4995.6  1270.8  5023.4 1271.48  5033.5 1273.03  5043.5  1277.3  5052.1 1279.91
  5123.9 1283.68  5212.8  1284.6  5259.9 1284.78  5311.6 1286.45  5515.8 1295.38
#Mann= 8 ,-1 , 0
    4444     .05       0  4669.4     .12       0  4746.3     .05       0
  4920.7     .12       0  4936.4     .05       0    4970     .12       0
  5212.8     .12       0  5311.6     .05       0
Bank Sta=4936.4,4970
XS Rating Curve= 0 ,0
Exp/Cntr=0.3,0.1

Type RM Length L Ch R = 1 ,500     ,0,0,0
BEGIN DESCRIPTION:
COLD CREEK 1.0
END DESCRIPTION:
XS GIS Cut Line= 3
      2742155.68     10273703.11      2741813.97     10272763.74
      2741305.67     10273153.12
#Sta/Elev= 30
  4000.4 1305.35  4071.5 1302.27  4096.2 1303.03  4102.1 1301.25  4107.5 1301.87
  4127.4 1299.85  4213.2 1295.48  4224.5 1293.63  4404.8 1284.37  4514.4 1282.76
  4702.7 1282.62  4890.8 1277.98  4921.3 1274.91  4926.7 1270.98  4951.9 1269.01
  4952.6 1268.51  4985.5 1269.01    4990    1270    5041 1269.88  5055.5 1272.03
  5061.8 1271.07    5070 1276.61  5076.3  1276.1  5084.6 1278.68  5090.9 1278.38
  5105.4 1281.39  5155.2 1281.82  5169.8 1283.08  5462.6 1284.47  5640.3 1290.79
#Mann= 3 ,-1 , 0
  4000.4     .05       0  4951.9     .05       0  4985.5     .05       0
Bank Sta=4951.9,4985.5
XS Rating Curve= 0 ,0
Exp/Cntr=0.3,0.1
Stream Node=COLD CREEK      ,Reach-1         , 0 , 0 ,Upstream end
Stream Node=COLD CREEK      ,Reach-1         , 0 , 1 ,Downstream end

Chan Stop Cuts=-1
Use User Specified Reach Order=0
Composite Channel Slope=5