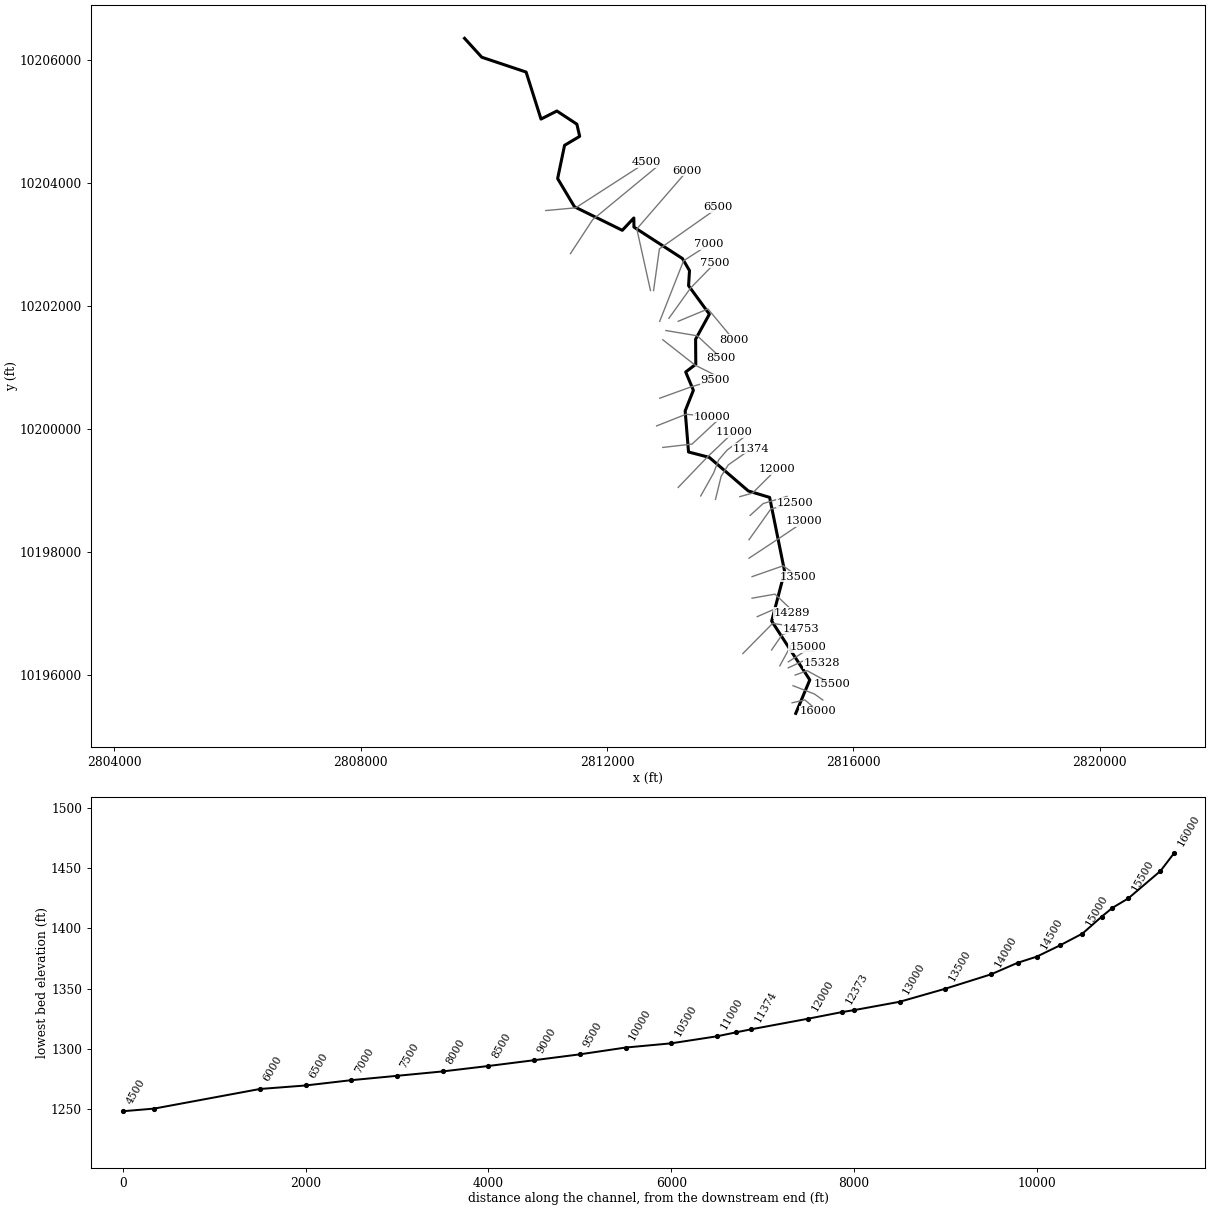
--- ELM HOLLOW CREEK.prj (project) ---

Proj Title=ELM HOLLOW CREEK Base Level Engineering
Current Plan=p01
Default Exp/Contr=0.3,0.1
English Units
Geom File=g01
Flow File=f01
Plan File=p01
BEGIN DESCRIPTION:
ELM HOLLOW CREEK
END DESCRIPTION:

--- ELM HOLLOW CREEK.p01 (plan) ---

Plan Title=Multiple Run
Short Identifier=Multiple
Geom File=g01
Flow File=f01
Subcritical Flow
K Sum by GR= 0
Std Step Tol= 0.01
Critical Tol= 0.01
Num of Std Step Trials= 20
Max Error Tol= 0.3
Flow Tol Ratio= 0.001
Split Flow NTrial= 30
Split Flow Tol= 0.02
Split Flow Ratio= 0.02
Log Output Level= 0
Friction Slope Method= 1
Unsteady Friction Slope Method= 2
Unsteady Bridges Friction Slope Method= 1
Parabolic Critical Depth
Global Vel Dist=  1 , 1 , 1
Global Log Level= 0
CheckData=True
Encroach Param= -1, 0, 0, 0
BEGIN DESCRIPTION:
Multiple Run
END DESCRIPTION:

--- ELM HOLLOW CREEK.f01 (steady flow) ---

Flow Title=Multiple
Number of Profiles=7
Profile Names=10-year,25-year,50-year,1pct_min,100-year,1pct_plu,500-year
River Rch & RM= ELM HOLLOW CREEK,Reach-1,16000
     412     666    1330     897    1861    3862    2702
River Rch & RM= ELM HOLLOW CREEK,Reach-1,6500
     728    1221    2372    1792    3362    6306    4829
River Rch & RM= ELM HOLLOW CREEK,Reach-1,401
     743    1246    2439    1547    3460    7739    4970
Boundary for River Rch & Prof#=ELM HOLLOW CREEK,Reach-1,1
Up Type=0
Dn Type=3
Dn Slope=0.005
Boundary for River Rch & Prof#=ELM HOLLOW CREEK,Reach-1,2
Up Type=0
Dn Type=3
Dn Slope=0.005
Boundary for River Rch & Prof#=ELM HOLLOW CREEK,Reach-1,3
Up Type=0
Dn Type=3
Dn Slope=0.005
Boundary for River Rch & Prof#=ELM HOLLOW CREEK,Reach-1,4
Up Type=0
Dn Type=3
Dn Slope=0.005
Boundary for River Rch & Prof#=ELM HOLLOW CREEK,Reach-1,5
Up Type=0
Dn Type=3
Dn Slope=0.005
Boundary for River Rch & Prof#=ELM HOLLOW CREEK,Reach-1,6
Up Type=0
Dn Type=3
Dn Slope=0.005
Boundary for River Rch & Prof#=ELM HOLLOW CREEK,Reach-1,7
Up Type=0
Dn Type=3
Dn Slope=0.005

--- ELM HOLLOW CREEK.g01 (geometry) ---

Geom Title=Existing Conditions

River Reach=ELM HOLLOW CREEK,Reach-1
Reach XY= 30
      2815065.00     10195381.00      2815293.00     10195925.00
      2814674.00     10196881.00      2814884.50     10197686.00
      2814640.75     10198891.00      2814294.25     10198996.00
      2813659.50     10199542.00      2813323.50     10199629.00
      2813269.00     10200296.00      2813402.25     10200632.00
      2813277.50     10200929.00      2813441.50     10201055.00
      2813438.25     10201462.00      2813662.25     10201869.00
      2813324.25     10202332.00      2813339.50     10202577.00
      2813224.75     10202773.00      2812437.25     10203284.00
      2812435.25     10203432.00      2812247.75     10203232.00
      2811470.75     10203615.00      2811197.75     10204073.00
      2811310.25     10204613.00      2811556.00     10204759.00
      2811510.25     10204957.00      2811185.25     10205171.00
      2810927.75     10205040.00      2810685.75     10205804.00
      2809965.75     10206045.00      2809686.50     10206352.00

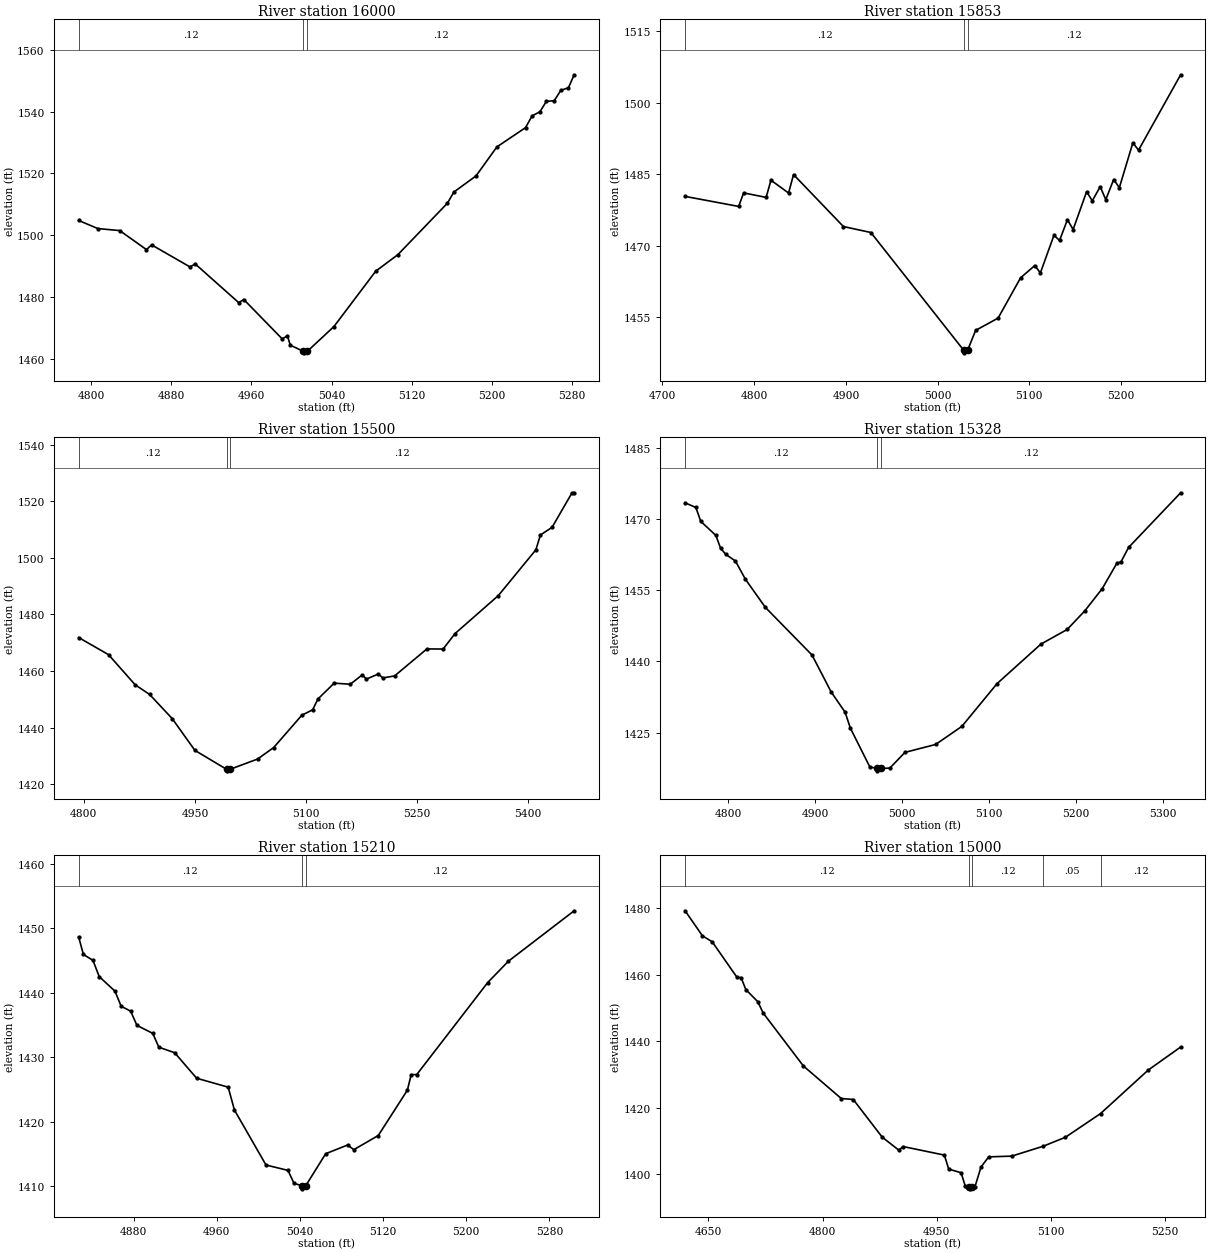
Type RM Length L Ch R = 1,16000,147,147,147
BEGIN DESCRIPTION:
ELM HOLLOW CREEK 32.0
END DESCRIPTION:
XS GIS Cut Line= 3
      2815005.71     10195553.12      2815213.00     10195599.40
      2815428.22     10195417.18
#Sta/Elev= 30
  4787.6 1504.81  4806.7 1502.19  4828.6 1501.53  4855.3 1495.38  4860.4 1496.92
  4898.7 1489.79  4903.9 1490.76  4947.3 1478.25  4952.4 1479.25  4990.7 1466.53
  4995.9 1467.50  4998.8 1464.49  5011.8 1462.52  5012.0 1462.02  5015.8 1462.52
  5042.3 1470.51  5084.0 1488.41  5106.1 1493.75  5155.5 1510.37  5162.0 1514.00
  5184.1 1519.21  5204.9 1528.58  5233.5 1534.81  5240.0 1538.61  5247.8 1539.92
  5254.3 1543.31  5262.1 1543.50  5268.6 1546.82  5276.3 1547.72  5282.0 1551.89
#Mann=3,-1,0
  4787.6    0.12       0  5011.8    0.07       0  5015.8    0.12       0
Bank Sta=5011.8,5015.8
Exp/Cntr=0.3,0.1

Type RM Length L Ch R = 1,15853,353,353,353
BEGIN DESCRIPTION:
Mapping XS d9abcc76
END DESCRIPTION:
XS GIS Cut Line= 3
      2815020.53     10195830.93      2815368.89     10195695.46
      2815504.32     10195598.73
#Sta/Elev= 30
  4724.7 1480.33  4783.1 1478.22  4788.5 1481.07  4813.0 1480.12  4818.3 1483.73
  4837.5 1481.04  4842.9 1484.92  4897.3 1473.99  4927.2 1472.74  5028.6 1447.94
  5028.9 1447.44  5032.6 1447.94  5041.4 1452.16  5065.9 1454.74  5090.4 1463.21
  5105.9 1465.79  5112.0 1464.25  5126.8 1472.15  5132.9 1471.07  5141.5 1475.43
  5147.7 1473.37  5162.4 1481.32  5168.6 1479.40  5177.2 1482.38  5183.3 1479.65
  5191.9 1483.88  5198.1 1482.17  5212.8 1491.59  5219.0 1490.06  5264.9 1505.90
#Mann=3,-1,0
  4724.7    0.12       0  5028.6    0.07       0  5032.6    0.12       0
Bank Sta=5028.6,5032.6
Exp/Cntr=0.3,0.1

Type RM Length L Ch R = 1,15500,172,172,172
BEGIN DESCRIPTION:
ELM HOLLOW CREEK 31.0
END DESCRIPTION:
XS GIS Cut Line= 3
      2815055.65     10196003.10      2815249.95     10196074.49
      2815655.69     10195853.11
#Sta/Elev= 30
  4793.0 1471.81  4833.4 1465.75  4869.2 1455.14  4888.9 1451.68  4919.5 1443.11
  4950.0 1431.92  4993.1 1425.19  4993.3 1424.69  4997.1 1425.19  5034.6 1428.85
  5056.4 1432.92  5094.4 1444.34  5109.1 1446.28  5116.2 1450.10  5138.1 1455.68
  5159.9 1455.30  5176.0 1458.61  5181.7 1457.13  5197.9 1458.93  5203.6 1457.52
  5219.7 1458.24  5263.3 1467.78  5285.2 1467.74  5301.3 1473.20  5359.7 1486.61
  5410.5 1502.82  5416.6 1508.05  5432.3 1510.74  5459.3 1522.97  5462.2 1522.97
#Mann=3,-1,0
  4793.0    0.12       0  4993.1    0.07       0  4997.1    0.12       0
Bank Sta=4993.1,4997.1
Exp/Cntr=0.3,0.1

Type RM Length L Ch R = 1,15328,118,118,118
BEGIN DESCRIPTION:
Mapping XS 3caecb06
END DESCRIPTION:
XS GIS Cut Line= 3
      2814943.12     10196121.17      2815194.73     10196237.30
      2815485.05     10196198.59
#Sta/Elev= 30
  4750.4 1473.41  4762.8 1472.43  4768.4 1469.51  4785.8 1466.54  4791.3 1463.81
  4797.3 1462.53  4808.3 1461.15  4819.7 1457.33  4842.7 1451.38  4896.4 1441.33
  4918.4 1433.55  4934.5 1429.26  4940.5 1425.92  4962.9 1417.74  4971.5 1417.42
  4971.7 1416.92  4975.5 1417.42  4985.9 1417.50  5003.3 1420.81  5038.6 1422.48
  5068.8 1426.30  5109.2 1435.30  5159.6 1443.62  5189.9 1446.72  5210.1 1450.63
  5230.2 1455.32  5246.9 1460.64  5251.9 1461.00  5260.5 1464.00  5320.4 1475.53
#Mann=3,-1,0
  4750.4    0.12       0  4971.5    0.07       0  4975.5    0.12       0
Bank Sta=4971.5,4975.5
Exp/Cntr=0.3,0.1

Type RM Length L Ch R = 1,15210,210,210,210
BEGIN DESCRIPTION:
Mapping XS 34b646ea
END DESCRIPTION:
XS GIS Cut Line= 3
      2814943.20     10196217.98      2815214.08     10196392.11
      2815368.86     10196392.11
#Sta/Elev= 30
  4827.1 1448.64  4831.7 1445.91  4840.9 1445.00  4846.9 1442.48  4862.1 1440.22
  4868.0 1437.89  4877.2 1437.12  4883.2 1434.92  4898.4 1433.69  4904.3 1431.54
  4919.5 1430.69  4940.6 1426.74  4971.0 1425.35  4977.0 1421.81  5007.4 1413.29
  5028.5 1412.46  5034.4 1410.44  5041.7 1410.10  5041.9 1409.60  5045.7 1410.10
  5064.8 1415.04  5085.9 1416.39  5091.9 1415.67  5115.4 1417.86  5143.4 1424.88
  5147.1 1427.30  5152.4 1427.30  5220.7 1441.56  5240.7 1444.88  5303.9 1452.68
#Mann=3,-1,0
  4827.1    0.12       0  5041.7    0.07       0  5045.7    0.12       0
Bank Sta=5041.7,5045.7
Exp/Cntr=0.3,0.1

Type RM Length L Ch R = 1,15000,247,247,247
BEGIN DESCRIPTION:
ELM HOLLOW CREEK 30.0
END DESCRIPTION:
XS GIS Cut Line= 3
      2814805.67     10196153.09      2814987.66     10196487.14
      2815255.71     10196453.11
#Sta/Elev= 30
  4619.6 1479.17  4642.4 1471.64  4655.2 1469.85  4687.5 1459.24  4693.2 1459.05
  4699.3 1455.50  4715.1 1451.83  4722.1 1448.44  4774.9 1432.53  4824.6 1422.75
  4840.4 1422.45  4878.4 1411.13  4900.2 1407.23  4905.9 1408.31  4960.0 1405.74
  4965.7 1401.54  4981.9 1400.44  4987.6 1396.31  4992.9 1396.10  4993.1 1395.60
  4996.9 1396.10  5000.0 1396.10  5008.1 1402.16  5018.2 1405.21  5048.4 1405.43
  5089.6 1408.39  5119.0 1411.11  5165.1 1418.23  5227.6 1431.29  5270.2 1438.22
#Mann=5,-1,0
  4619.6    0.12       0  4992.9    0.07       0  4996.9    0.12       0
  5089.6    0.05       0  5165.1    0.12       0
Bank Sta=4992.9,4996.9
Exp/Cntr=0.3,0.1

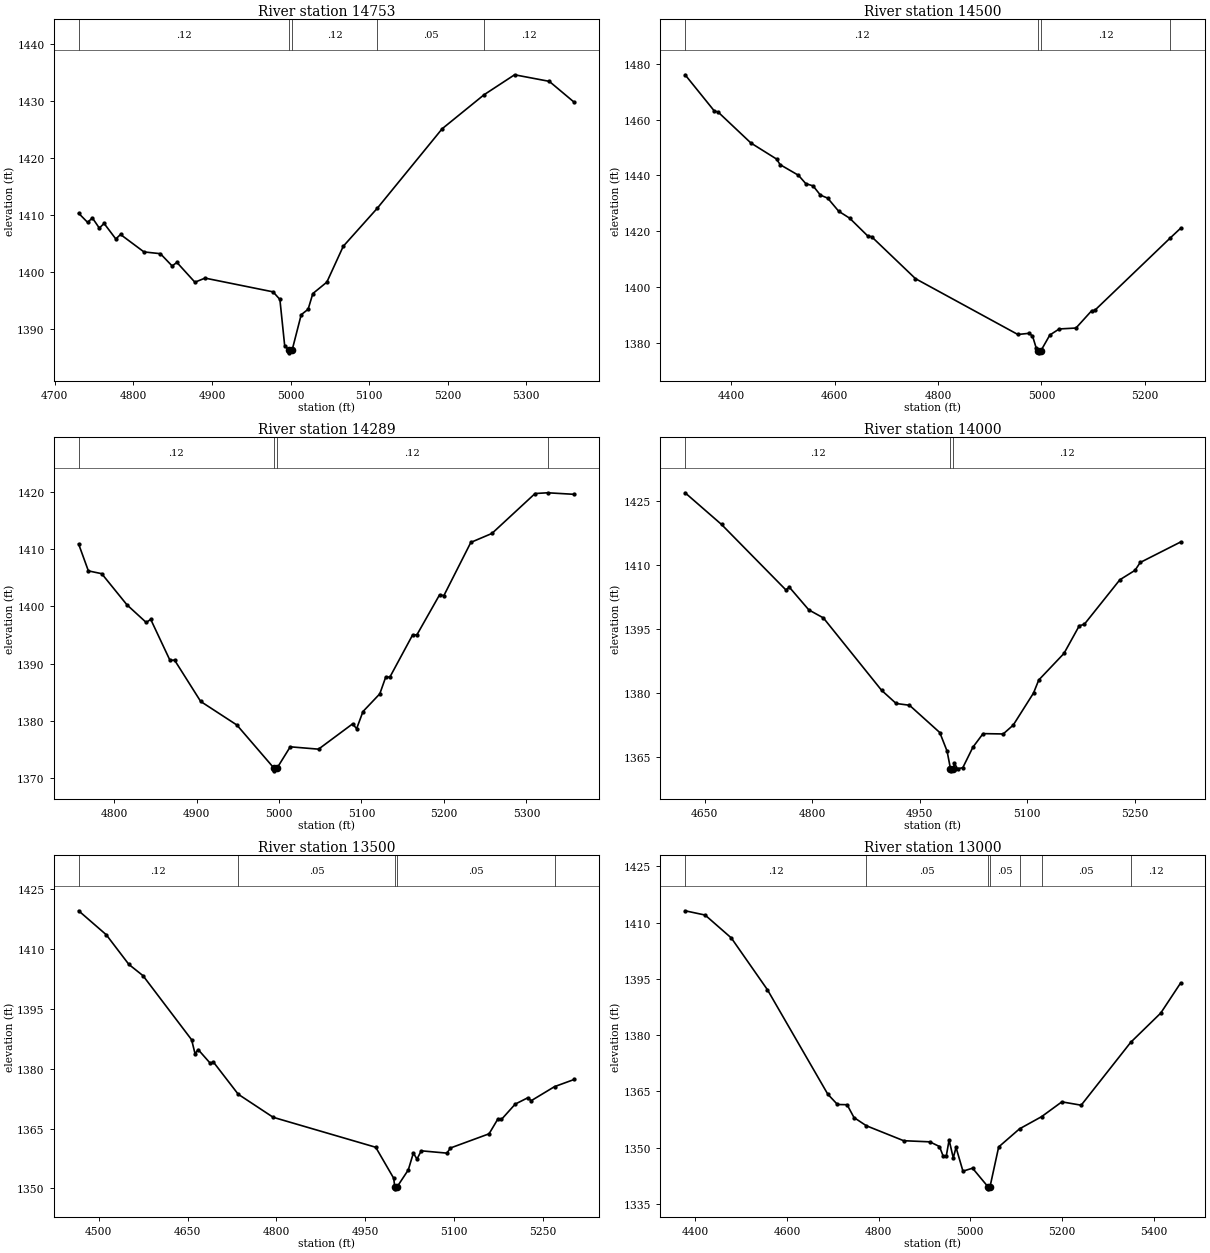
Type RM Length L Ch R = 1,14753,253,253,253
BEGIN DESCRIPTION:
Mapping XS 914c2d87
END DESCRIPTION:
XS GIS Cut Line= 3
      2814672.25     10196411.48      2814846.41     10196663.03
      2815155.99     10196759.78
#Sta/Elev= 30
  4730.5 1410.25  4741.9 1408.65  4748.0 1409.43  4756.8 1407.65  4762.9 1408.46
  4777.8 1405.74  4783.8 1406.53  4813.6 1403.47  4834.5 1403.16  4849.4 1401.01
  4855.5 1401.63  4878.4 1398.16  4891.3 1398.88  4977.8 1396.47  4986.5 1395.14
  4992.6 1387.01  4998.1 1386.28  4998.3 1385.78  5002.1 1386.28  5013.6 1392.46
  5022.4 1393.42  5028.4 1396.17  5046.2 1398.17  5067.1 1404.46  5110.4 1411.13
  5192.9 1425.06  5246.2 1431.02  5285.0 1434.52  5329.1 1433.37  5360.8 1429.71
#Mann=5,-1,0
  4730.5    0.12       0  4998.1    0.07       0  5002.1    0.12       0
  5110.4    0.05       0  5246.2    0.12       0
Bank Sta=4998.1,5002.1
Exp/Cntr=0.3,0.1

Type RM Length L Ch R = 1,14500,211,211,211
BEGIN DESCRIPTION:
ELM HOLLOW CREEK 29.0
END DESCRIPTION:
XS GIS Cut Line= 3
      2814205.67     10196353.10      2814689.70     10196843.73
      2814955.72     10196803.11
#Sta/Elev= 30
  4310.8 1476.03  4367.3 1463.07  4374.5 1462.71  4438.1 1451.60  4487.6 1445.87
  4494.6 1443.85  4530.0 1440.05  4544.2 1437.06  4558.3 1436.25  4572.5 1432.95
  4586.6 1431.86  4607.8 1427.18  4629.0 1424.69  4664.3 1418.27  4671.5 1418.06
  4756.3 1403.04  4954.3 1383.05  4975.5 1383.46  4982.6 1382.56  4989.6 1378.32
  4994.1 1376.98  4994.3 1376.48  4998.1 1376.98  5016.2 1382.87  5034.3 1385.03
  5066.7 1385.36  5097.1 1391.57  5102.8 1391.65  5249.4 1417.68  5269.1 1421.09
#Mann=4,-1,0
  4310.8    0.12       0  4994.1    0.07       0  4998.1    0.12       0
  5249.4    0.05       0
Bank Sta=4994.1,4998.1
Exp/Cntr=0.3,0.1

Type RM Length L Ch R = 1,14289,289,289,289
BEGIN DESCRIPTION:
Mapping XS 60c9c499
END DESCRIPTION:
XS GIS Cut Line= 3
      2814440.05     10196953.32      2814749.65     10197088.76
      2815000.99     10197011.43
#Sta/Elev= 30
  4757.0 1410.87  4768.8 1406.19  4785.0 1405.70  4815.6 1400.27  4839.0 1397.19
  4844.4 1397.74  4867.8 1390.58  4873.3 1390.64  4905.0 1383.42  4948.9 1379.31
  4993.7 1371.82  4993.9 1371.32  4997.7 1371.82  5013.6 1375.51  5047.9 1375.10
  5089.2 1379.51  5094.1 1378.67  5101.8 1381.66  5122.2 1384.75  5129.3 1387.64
  5134.5 1387.69  5162.0 1395.02  5167.2 1395.04  5194.7 1402.02  5199.9 1401.88
  5232.6 1411.16  5258.2 1412.72  5310.5 1419.68  5325.8 1419.81  5357.9 1419.54
#Mann=4,-1,0
  4757.0    0.12       0  4993.7    0.07       0  4997.7    0.12       0
  5325.8    0.05       0
Bank Sta=4993.7,4997.7
Exp/Cntr=0.3,0.1

Type RM Length L Ch R = 1,14000,500,500,500
BEGIN DESCRIPTION:
ELM HOLLOW CREEK 28.0
END DESCRIPTION:
XS GIS Cut Line= 3
      2814355.66     10197253.11      2814727.42     10197318.71
      2814955.69     10197103.11
#Sta/Elev= 30
  4622.5 1426.81  4673.3 1419.41  4763.0 1404.13  4768.1 1404.72  4795.2 1399.43
  4815.5 1397.56  4896.7 1380.64  4917.0 1377.56  4935.6 1377.15  4977.9 1370.77
  4988.1 1366.42  4992.8 1362.32  4993.1 1361.82  4996.8 1362.32  4998.3 1363.57
  5002.7 1362.32  5010.0 1362.55  5024.1 1367.34  5038.3 1370.52  5066.4 1370.44
  5080.4 1372.51  5108.7 1380.00  5116.0 1383.05  5151.2 1389.26  5172.6 1395.74
  5179.5 1396.05  5229.2 1406.48  5250.3 1408.68  5257.6 1410.52  5314.0 1415.31
#Mann=3,-1,0
  4622.5    0.12       0  4992.8    0.07       0  4996.8    0.12       0
Bank Sta=4992.8,4996.8
Exp/Cntr=0.3,0.1

Type RM Length L Ch R = 1,13500,500,500,500
BEGIN DESCRIPTION:
ELM HOLLOW CREEK 27.0
END DESCRIPTION:
XS GIS Cut Line= 3
      2814355.66     10197603.10      2814859.53     10197779.34
      2815105.66     10197603.13
#Sta/Elev= 30
  4466.2 1419.58  4512.8 1413.58  4551.0 1406.14  4574.9 1403.31  4656.9 1387.26
  4662.7 1383.76  4668.0 1384.79  4688.4 1381.36  4693.7 1381.67  4735.6 1373.60
  4794.6 1367.82  4967.7 1360.31  4998.1 1352.53  4999.8 1350.39  5000.0 1349.89
  5003.8 1350.39  5022.7 1354.64  5031.2 1358.84  5037.4 1357.35  5044.5 1359.42
  5087.8 1358.84  5093.9 1360.13  5159.0 1363.68  5173.7 1367.34  5179.9 1367.28
  5203.2 1371.13  5224.1 1372.69  5230.3 1371.99  5269.6 1375.51  5302.7 1377.30
#Mann=5,-1,0
  4466.2    0.12       0  4735.6    0.05       0  4999.8    0.05       0
  5003.8    0.05       0  5269.6    0.12       0
Bank Sta=4999.8,5003.8
Exp/Cntr=0.3,0.1

Type RM Length L Ch R = 1,13000,500,500,500
BEGIN DESCRIPTION:
ELM HOLLOW CREEK 26.0
END DESCRIPTION:
XS GIS Cut Line= 3
      2814305.67     10197903.10      2814825.16     10198246.45
      2815205.69     10198503.12
#Sta/Elev= 30
  4377.3 1413.13  4421.0 1411.99  4478.1 1405.90  4557.1 1392.08  4688.8 1364.27
  4709.9 1361.53  4730.9 1361.47  4746.0 1358.05  4772.9 1355.87  4854.4 1351.88
  4911.5 1351.58  4932.6 1350.33  4940.7 1347.75  4947.6 1347.92  4953.6 1352.07
  4962.7 1347.28  4968.7 1350.10  4983.8 1343.77  5004.8 1344.56  5038.8 1339.56
  5039.0 1339.06  5042.8 1339.56  5061.8 1350.22  5107.3 1355.04  5155.5 1358.29
  5199.7 1362.23  5241.9 1361.34  5350.1 1378.10  5415.5 1385.87  5459.0 1393.90
#Mann=7,-1,0
  4377.3    0.12       0  4772.9    0.05       0  5038.8    0.05       0
  5042.8    0.05       0  5107.3    0.12       0  5155.5    0.05       0
  5350.1    0.12       0
Bank Sta=5038.8,5042.8
Exp/Cntr=0.3,0.1

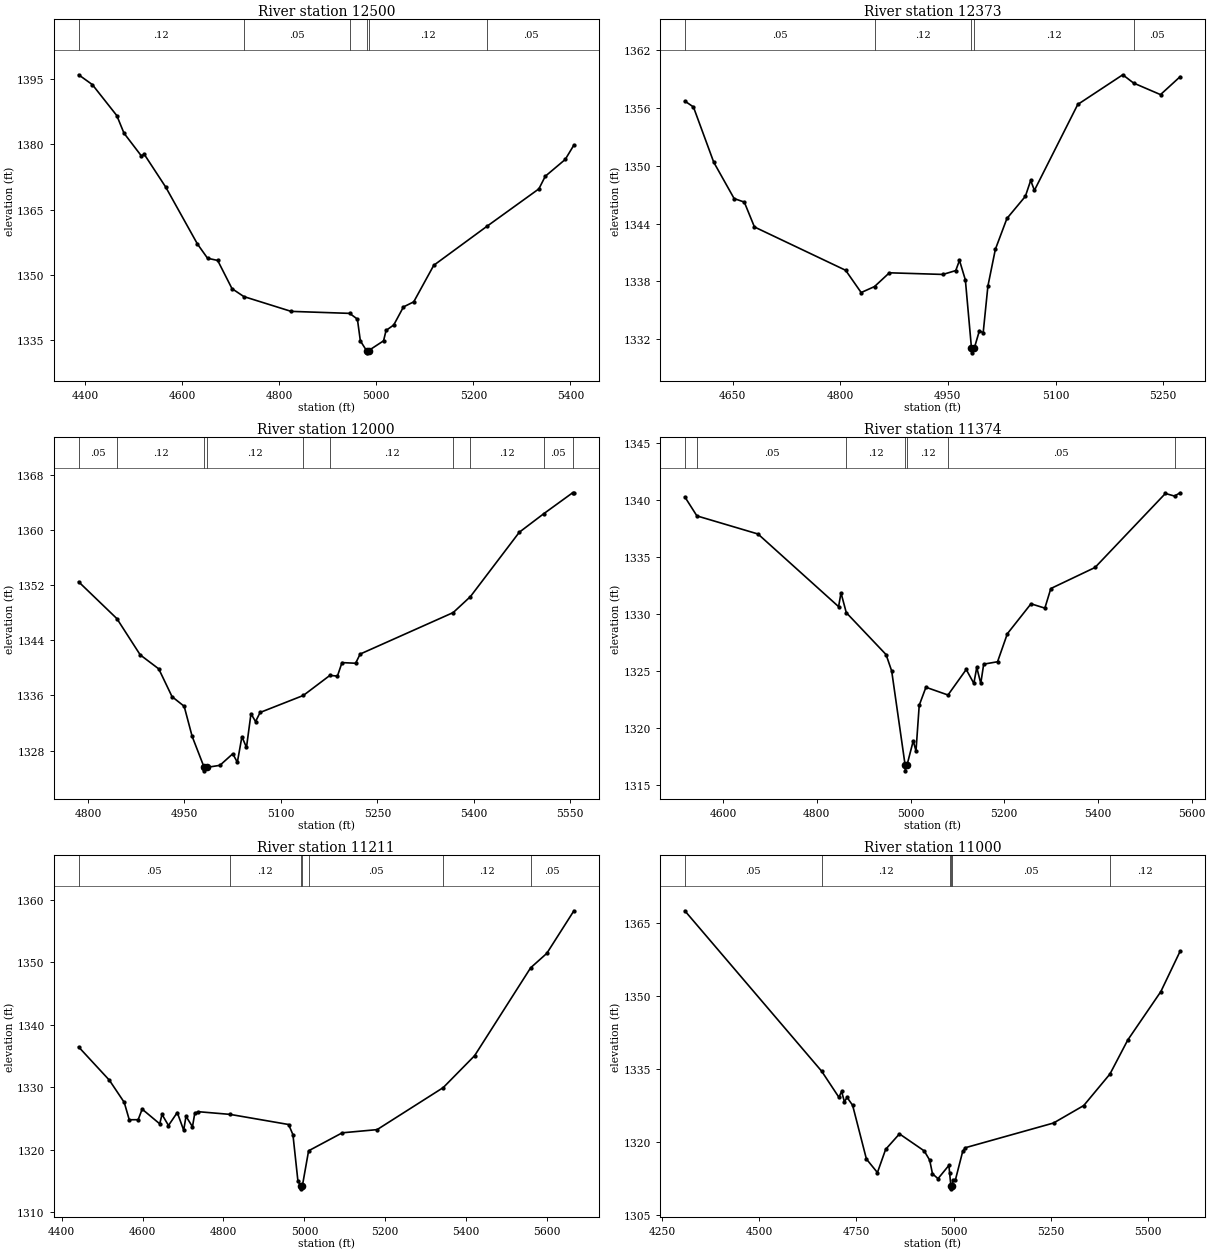
Type RM Length L Ch R = 1,12500,127,127,127
BEGIN DESCRIPTION:
ELM HOLLOW CREEK 25.0
END DESCRIPTION:
XS GIS Cut Line= 3
      2814305.68     10198203.11      2814660.82     10198703.25
      2815055.69     10198803.11
#Sta/Elev= 30
  4386.6 1396.02  4414.9 1393.76  4465.3 1386.64  4480.1 1382.60  4515.8 1377.39
  4521.9 1377.74  4566.2 1370.19  4631.4 1357.14  4652.3 1353.86  4673.2 1353.35
  4702.7 1346.87  4727.1 1345.05  4824.5 1341.65  4945.1 1341.19  4961.1 1339.87
  4967.2 1334.87  4980.0 1332.62  4980.2 1332.12  4984.0 1332.62  5015.0 1334.88
  5020.2 1337.27  5036.0 1338.52  5056.0 1342.67  5077.2 1343.84  5118.5 1352.24
  5228.2 1361.21  5335.1 1369.80  5348.3 1372.70  5389.4 1376.56  5407.3 1379.87
#Mann=6,-1,0
  4386.6    0.12       0  4727.1    0.05       0  4945.1    0.12       0
  4980.0    0.07       0  4984.0    0.12       0  5228.2    0.05       0
Bank Sta=4980,4984
Exp/Cntr=0.3,0.1

Type RM Length L Ch R = 1,12373,373,373,373
BEGIN DESCRIPTION:
Mapping XS 70225c0c
END DESCRIPTION:
XS GIS Cut Line= 3
      2814323.91     10198598.17      2814536.78     10198791.69
      2814922.22     10198907.33
#Sta/Elev= 30
  4583.5 1356.73  4595.5 1356.12  4623.8 1350.38  4652.2 1346.61  4666.4 1346.24
  4680.5 1343.66  4807.6 1339.16  4829.2 1336.85  4847.8 1337.47  4868.5 1338.90
  4943.1 1338.73  4961.0 1339.13  4966.2 1340.19  4974.4 1338.16  4982.9 1331.09
  4983.1 1330.59  4986.9 1331.09  4994.0 1332.90  4999.2 1332.66  5005.8 1337.52
  5016.2 1341.34  5032.3 1344.54  5058.0 1346.84  5065.4 1348.49  5070.6 1347.46
  5131.0 1356.38  5193.7 1359.46  5208.8 1358.60  5246.3 1357.40  5273.6 1359.26
#Mann=5,-1,0
  4583.5    0.05       0  4847.8    0.12       0  4982.9    0.07       0
  4986.9    0.12       0  5208.8    0.05       0
Bank Sta=4982.9,4986.9
Exp/Cntr=0.3,0.1

Type RM Length L Ch R = 1,12000,626,626,626
BEGIN DESCRIPTION:
ELM HOLLOW CREEK 24.0
END DESCRIPTION:
XS GIS Cut Line= 3
      2814155.71     10198903.12      2814362.32     10198960.77
      2814755.70     10199353.13
#Sta/Elev= 30
  4785.5 1352.51  4845.0 1347.16  4881.3 1341.89  4910.1 1339.86  4930.8 1335.82
  4949.6 1334.43  4962.0 1330.06  4980.7 1325.55  4981.0 1325.05  4984.7 1325.55
  5005.2 1325.85  5025.2 1327.53  5032.3 1326.29  5039.4 1330.01  5046.5 1328.45
  5053.5 1333.35  5060.6 1332.21  5067.7 1333.53  5134.9 1336.00  5176.3 1338.92
  5187.9 1338.81  5195.0 1340.77  5216.2 1340.68  5223.2 1342.01  5367.9 1348.04
  5394.7 1350.36  5470.7 1359.71  5509.0 1362.42  5553.6 1365.44  5555.6 1365.44
#Mann=10,-1,0
  4785.5    0.05       0  4845.0    0.12       0  4980.7    0.07       0
  4984.7    0.12       0  5134.9    0.05       0  5176.3    0.12       0
  5367.9    0.05       0  5394.7    0.12       0  5509.0    0.05       0
  5553.6    0.12       0
Bank Sta=4980.7,4984.7
Exp/Cntr=0.3,0.1

Type RM Length L Ch R = 1,11374,163,163,163
BEGIN DESCRIPTION:
Mapping XS 36c39f7d
END DESCRIPTION:
XS GIS Cut Line= 4
      2813762.08     10198861.36      2813853.64     10199235.20
      2813968.09     10199418.32      2814341.32     10199681.11
#Sta/Elev= 30
  4518.1 1340.29  4543.9 1338.62  4674.3 1337.03  4846.4 1330.65  4851.5 1331.86
  4862.8 1330.12  4947.7 1326.44  4959.7 1325.00  4988.4 1316.73  4988.6 1316.23
  4992.4 1316.73  5005.7 1318.86  5011.6 1317.97  5018.5 1321.99  5032.8 1323.57
  5079.9 1322.89  5118.8 1325.13  5135.1 1323.91  5141.3 1325.31  5149.9 1323.91
  5156.1 1325.60  5185.7 1325.81  5206.6 1328.27  5257.1 1330.90  5286.7 1330.52
  5299.4 1332.24  5393.8 1334.09  5544.0 1340.59  5563.5 1340.36  5575.4 1340.65
#Mann=7,-1,0
  4518.1    0.12       0  4543.9    0.05       0  4862.8    0.12       0
  4988.4    0.07       0  4992.4    0.12       0  5079.9    0.05       0
  5563.5    0.12       0
Bank Sta=4988.4,4992.4
Exp/Cntr=0.3,0.1

Type RM Length L Ch R = 1,11211,211,211,211
BEGIN DESCRIPTION:
Mapping XS b6b29d96
END DESCRIPTION:
XS GIS Cut Line= 5
      2813521.73     10198914.74      2813731.55     10199288.61
      2813811.67     10199498.44      2813949.01     10199658.67
      2814233.98     10199879.05
#Sta/Elev= 30
  4441.8 1336.47  4517.9 1331.14  4554.6 1327.59  4567.0 1324.81  4589.0 1324.82
  4598.9 1326.51  4642.3 1324.16  4648.0 1325.66  4664.0 1323.89  4685.7 1325.97
  4701.6 1323.13  4707.3 1325.37  4723.3 1323.69  4729.0 1325.85  4738.1 1326.10
  4816.3 1325.67  4961.0 1324.05  4971.7 1322.42  4984.0 1315.01  4991.1 1314.25
  4991.3 1313.75  4995.1 1314.25  5010.4 1319.84  5093.6 1322.72  5179.8 1323.23
  5343.3 1329.96  5420.9 1335.07  5559.4 1349.14  5599.3 1351.45  5666.4 1358.27
#Mann=7,-1,0
  4441.8    0.05       0  4816.3    0.12       0  4991.1    0.07       0
  4995.1    0.12       0  5010.4    0.05       0  5343.3    0.12       0
  5559.4    0.05       0
Bank Sta=4991.1,4995.1
Exp/Cntr=0.3,0.1

Type RM Length L Ch R = 1,11000,500,500,500
BEGIN DESCRIPTION:
ELM HOLLOW CREEK 22.0
END DESCRIPTION:
XS GIS Cut Line= 3
      2813155.71     10199053.14      2813634.00     10199552.00
      2814055.69     10199953.12
#Sta/Elev= 30
  4308.9 1367.56  4660.7 1334.60  4705.0 1329.24  4711.9 1330.45  4719.1 1328.32
  4726.0 1329.22  4740.2 1327.61  4775.7 1316.56  4804.0 1313.78  4825.1 1318.55
  4860.6 1321.73  4924.2 1318.24  4938.3 1316.34  4945.5 1313.53  4959.7 1312.53
  4987.7 1315.26  4989.7 1313.60  4992.9 1310.94  4993.2 1310.44  4996.9 1310.94
  4997.6 1312.27  5004.4 1312.27  5023.2 1318.14  5030.1 1318.89  5256.6 1323.96
  5334.3 1327.55  5401.7 1334.03  5447.5 1341.02  5532.4 1350.95  5582.0 1359.24
#Mann=6,-1,0
  4308.9    0.05       0  4660.7    0.12       0  4989.7    0.05       0
  4992.9    0.05       0  4996.9    0.05       0  5401.7    0.12       0
Bank Sta=4992.9,4996.9
Exp/Cntr=0.3,0.1

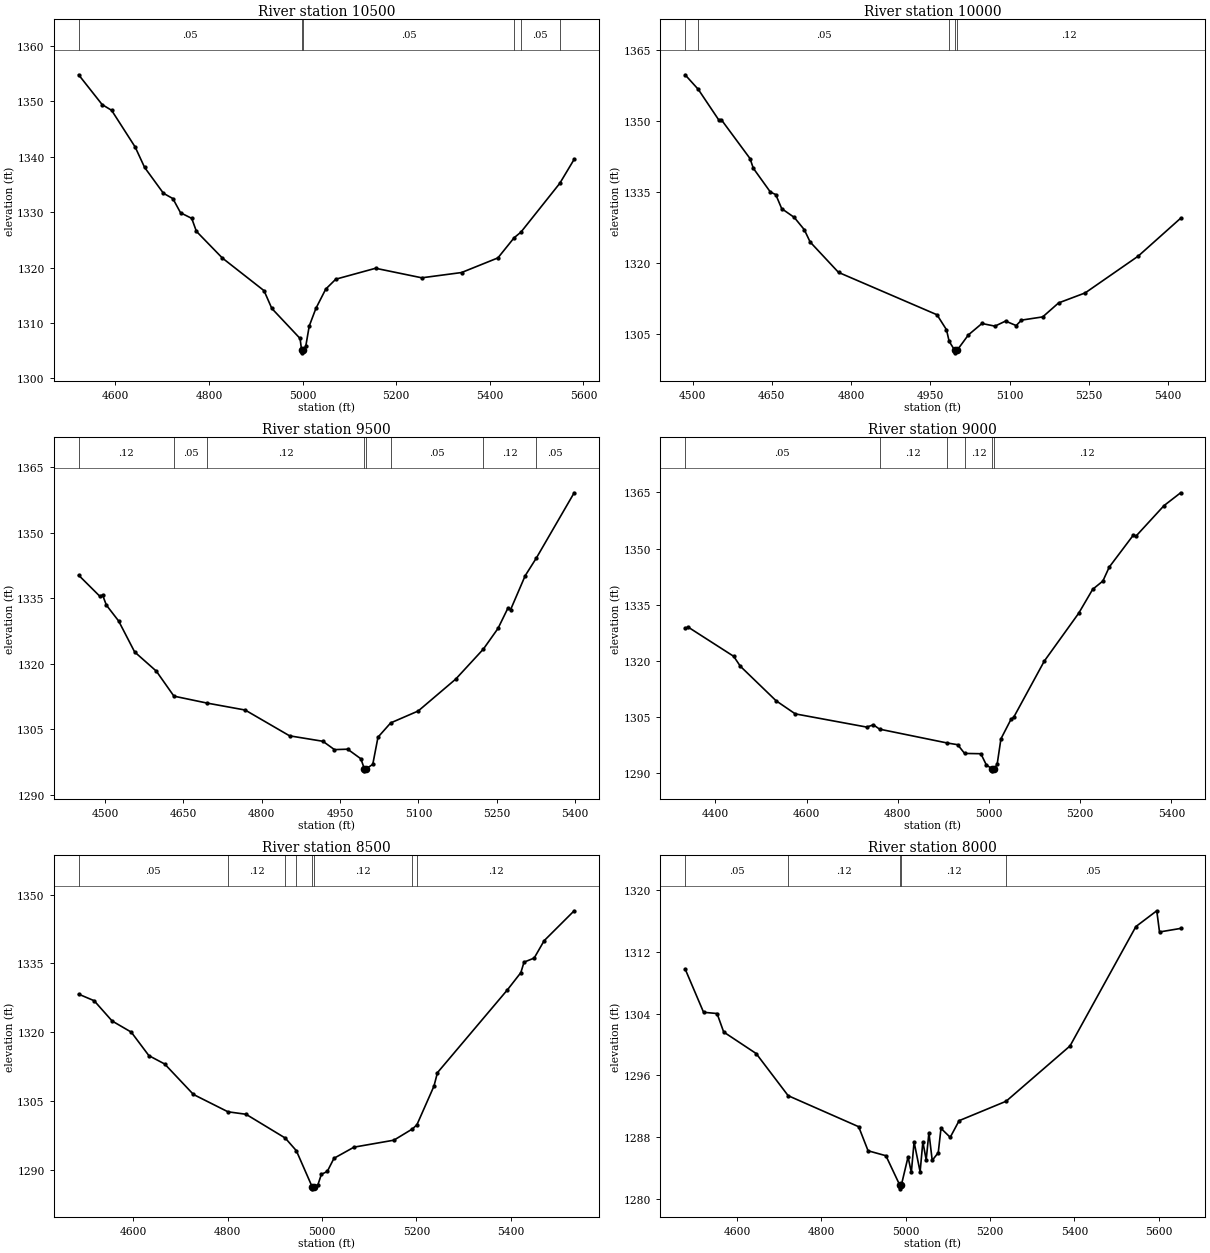
Type RM Length L Ch R = 1,10500,500,500,500
BEGIN DESCRIPTION:
ELM HOLLOW CREEK 21.0
END DESCRIPTION:
XS GIS Cut Line= 3
      2812905.68     10199703.11      2813380.96     10199757.67
      2813805.67     10200153.10
#Sta/Elev= 30
  4521.6 1354.76  4571.9 1349.38  4592.1 1348.35  4642.4 1341.73  4662.5 1338.06
  4702.8 1333.39  4722.9 1332.44  4739.4 1329.87  4763.2 1328.87  4773.2 1326.53
  4828.6 1321.72  4917.7 1315.83  4934.3 1312.63  4994.7 1307.21  4997.9 1305.12
  4998.1 1304.62  5001.9 1305.12  5007.0 1305.88  5014.3 1309.46  5028.5 1312.63
  5049.5 1316.11  5071.0 1317.90  5156.0 1319.87  5254.7 1318.15  5339.7 1319.10
  5417.4 1321.74  5452.1 1325.38  5466.5 1326.38  5549.5 1335.18  5580.3 1339.52
#Mann=6,-1,0
  4521.6    0.05       0  4997.9    0.05       0  5001.9    0.05       0
  5452.1    0.12       0  5466.5    0.05       0  5549.5    0.12       0
Bank Sta=4997.9,5001.9
Exp/Cntr=0.3,0.1

Type RM Length L Ch R = 1,10000,500,500,500
BEGIN DESCRIPTION:
ELM HOLLOW CREEK 20.0
END DESCRIPTION:
XS GIS Cut Line= 3
      2812805.68     10200053.11      2813283.69     10200242.61
      2813705.64     10200203.12
#Sta/Elev= 30
  4485.8 1359.76  4510.7 1356.69  4549.3 1350.27  4554.7 1350.24  4608.7 1342.09
  4614.9 1340.05  4647.2 1335.03  4657.4 1334.49  4668.7 1331.52  4692.4 1329.68
  4711.4 1327.09  4722.5 1324.49  4776.2 1318.08  4962.6 1309.14  4980.6 1305.98
  4985.6 1303.54  4996.4 1301.61  4996.6 1301.11  5000.4 1301.61  5022.1 1304.90
  5047.7 1307.30  5072.3 1306.74  5092.4 1307.81  5112.5 1306.86  5122.5 1308.01
  5162.7 1308.69  5192.8 1311.64  5243.1 1313.75  5343.5 1321.51  5423.8 1329.50
#Mann=5,-1,0
  4485.8    0.12       0  4510.7    0.05       0  4985.6    0.12       0
  4996.4    0.07       0  5000.4    0.12       0
Bank Sta=4996.4,5000.4
Exp/Cntr=0.3,0.1

Type RM Length L Ch R = 1,9500,500,500,500
BEGIN DESCRIPTION:
ELM HOLLOW CREEK 19.0
END DESCRIPTION:
XS GIS Cut Line= 3
      2812855.73     10200503.13      2813373.63     10200690.34
      2813755.64     10200803.10
#Sta/Elev= 30
  4449.3 1340.31  4489.9 1335.48  4495.2 1335.76  4502.4 1333.46  4525.9 1329.82
  4556.6 1322.72  4598.1 1318.33  4631.8 1312.60  4695.3 1311.01  4768.2 1309.42
  4853.3 1303.51  4917.1 1302.26  4939.2 1300.35  4964.5 1300.45  4989.8 1298.25
  4996.4 1295.99  4996.7 1295.49  5000.4 1295.99  5012.6 1296.98  5022.6 1303.20
  5046.9 1306.47  5099.6 1309.20  5171.5 1316.51  5224.4 1323.38  5252.4 1328.11
  5271.4 1332.76  5276.6 1332.43  5304.5 1340.19  5326.1 1344.29  5398.3 1359.19
#Mann=8,-1,0
  4449.3    0.12       0  4631.8    0.05       0  4695.3    0.12       0
  4996.4    0.07       0  5000.4    0.12       0  5046.9    0.05       0
  5224.4    0.12       0  5326.1    0.05       0
Bank Sta=4996.4,5000.4
Exp/Cntr=0.3,0.1

Type RM Length L Ch R = 1,9000,500,500,500
BEGIN DESCRIPTION:
ELM HOLLOW CREEK 18.0
END DESCRIPTION:
XS GIS Cut Line= 3
      2812905.69     10201453.11      2813429.70     10201041.07
      2813805.73     10200853.09
#Sta/Elev= 30
  4333.4 1328.79  4340.6 1328.97  4440.0 1321.21  4454.5 1318.57  4533.1 1309.33
  4575.1 1305.84  4731.9 1302.31  4746.4 1302.92  4760.0 1301.76  4908.2 1298.07
  4931.3 1297.61  4946.5 1295.28  4982.2 1295.20  4994.3 1292.18  5007.4 1291.13
  5007.7 1290.63  5011.4 1291.13  5017.9 1292.37  5026.2 1299.17  5048.6 1304.46
  5054.2 1304.93  5121.3 1319.93  5196.8 1332.72  5227.5 1339.11  5249.8 1341.31
  5263.8 1345.04  5316.9 1353.62  5322.5 1353.31  5384.0 1361.46  5420.4 1364.88
#Mann=6,-1,0
  4333.4    0.05       0  4760.0    0.12       0  4908.2    0.05       0
  4946.5    0.12       0  5007.4    0.07       0  5011.4    0.12       0
Bank Sta=5007.4,5011.4
Exp/Cntr=0.3,0.1

Type RM Length L Ch R = 1,8500,500,500,500
BEGIN DESCRIPTION:
ELM HOLLOW CREEK 17.0
END DESCRIPTION:
XS GIS Cut Line= 3
      2812955.66     10201603.12      2813464.64     10201517.65
      2813855.68     10201153.12
#Sta/Elev= 30
  4483.9 1328.29  4516.8 1326.86  4554.9 1322.44  4595.5 1320.01  4632.9 1314.88
  4666.4 1313.06  4727.3 1306.42  4800.5 1302.64  4838.8 1302.10  4921.9 1296.92
  4945.5 1294.16  4978.8 1286.34  4979.0 1285.84  4982.8 1286.34  4990.9 1286.62
  4998.6 1289.00  5011.1 1289.63  5025.3 1292.50  5067.8 1294.93  5152.3 1296.45
  5191.8 1298.91  5201.2 1299.82  5237.3 1308.23  5244.7 1311.17  5393.2 1329.25
  5421.5 1332.98  5428.3 1335.27  5449.8 1336.16  5470.9 1339.94  5534.6 1346.47
#Mann=8,-1,0
  4483.9    0.05       0  4800.5    0.12       0  4921.9    0.05       0
  4945.5    0.12       0  4978.8    0.07       0  4982.8    0.12       0
  5191.8    0.05       0  5201.2    0.12       0
Bank Sta=4978.8,4982.8
Exp/Cntr=0.3,0.1

Type RM Length L Ch R = 1,8000,500,500,500
BEGIN DESCRIPTION:
ELM HOLLOW CREEK 16.0
END DESCRIPTION:
XS GIS Cut Line= 3
      2813155.72     10201753.13      2813638.73     10201954.22
      2814055.69     10201453.10
#Sta/Elev= 30
  4476.8 1309.77  4520.6 1304.16  4552.6 1304.00  4568.3 1301.61  4645.3 1298.83
  4721.2 1293.38  4888.4 1289.37  4910.7 1286.26  4953.0 1285.62  4985.7 1281.84
  4985.9 1281.34  4989.7 1281.84  5005.5 1285.46  5013.3 1283.48  5019.8 1287.40
  5034.1 1283.54  5040.6 1287.41  5048.5 1285.09  5055.0 1288.60  5062.8 1285.02
  5077.1 1286.01  5083.6 1289.16  5105.5 1288.00  5126.6 1290.15  5238.0 1292.66
  5389.6 1299.81  5545.8 1315.24  5595.3 1317.28  5601.8 1314.54  5651.9 1315.00
#Mann=5,-1,0
  4476.8    0.05       0  4721.2    0.12       0  4985.7    0.07       0
  4989.7    0.12       0  5238.0    0.05       0
Bank Sta=4985.7,4989.7
Exp/Cntr=0.3,0.1

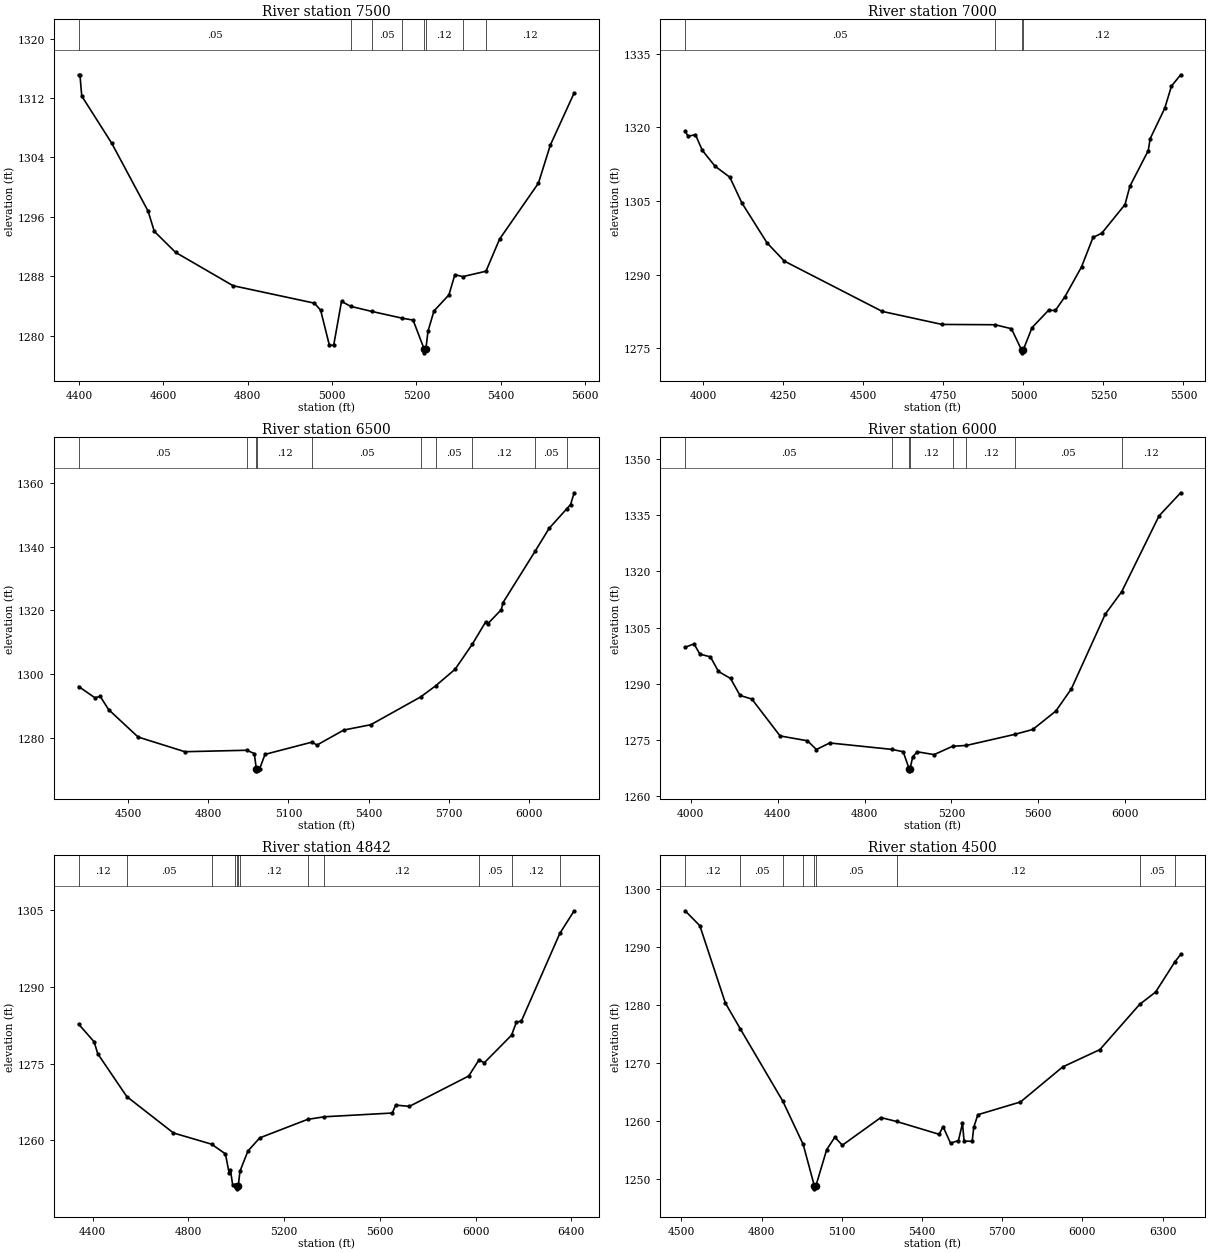
Type RM Length L Ch R = 1,7500,500,500,500
BEGIN DESCRIPTION:
ELM HOLLOW CREEK 15.0
END DESCRIPTION:
XS GIS Cut Line= 3
      2813005.68     10201803.10      2813355.38     10202291.89
      2813755.69     10202703.12
#Sta/Elev= 30
  4399.0 1315.13  4402.1 1315.13  4406.4 1312.27  4477.6 1305.90  4563.6 1296.78
  4578.4 1294.05  4628.8 1291.22  4765.1 1286.73  4958.0 1284.38  4972.8 1283.43
  4993.6 1278.69  5003.8 1278.73  5022.3 1284.62  5043.9 1283.95  5093.7 1283.27
  5166.6 1282.35  5192.0 1282.10  5218.3 1278.19  5218.6 1277.69  5222.3 1278.19
  5227.3 1280.59  5241.5 1283.33  5276.9 1285.49  5291.1 1288.22  5309.7 1287.95
  5364.8 1288.68  5397.1 1293.01  5489.1 1300.53  5517.4 1305.66  5573.9 1312.69
#Mann=8,-1,0
  4399.0    0.05       0  5043.9    0.12       0  5093.7    0.05       0
  5166.6    0.12       0  5218.3    0.05       0  5222.3    0.12       0
  5309.7    0.05       0  5364.8    0.12       0
Bank Sta=5218.3,5222.3
Exp/Cntr=0.3,0.1

Type RM Length L Ch R = 1,7000,500,500,500
BEGIN DESCRIPTION:
ELM HOLLOW CREEK 14.0
END DESCRIPTION:
XS GIS Cut Line= 3
      2812855.68     10201753.10      2813242.97     10202736.48
      2813655.65     10203003.09
#Sta/Elev= 30
  3943.1 1319.19  3952.6 1318.18  3975.4 1318.50  3996.9 1315.30  4036.5 1312.09
  4082.8 1309.84  4120.5 1304.60  4199.0 1296.48  4253.2 1292.76  4559.1 1282.52
  4746.0 1279.87  4911.4 1279.81  4962.6 1279.00  4994.9 1274.59  4995.1 1274.09
  4998.9 1274.59  5027.2 1279.24  5078.7 1282.76  5099.8 1282.71  5130.1 1285.55
  5181.6 1291.58  5217.5 1297.58  5244.9 1298.44  5317.5 1304.28  5332.7 1308.00
  5390.1 1315.25  5396.1 1317.69  5441.5 1323.85  5462.6 1328.38  5491.3 1330.69
#Mann=4,-1,0
  3943.1    0.05       0  4911.4    0.12       0  4994.9    0.07       0
  4998.9    0.12       0
Bank Sta=4994.9,4998.9
Exp/Cntr=0.3,0.1

Type RM Length L Ch R = 1,6500,500,500,500
BEGIN DESCRIPTION:
ELM HOLLOW CREEK 13.0
END DESCRIPTION:
XS GIS Cut Line= 3
      2812755.68     10202253.09      2812850.91     10202930.83
      2813805.67     10203603.10
#Sta/Elev= 30
  4315.6 1296.15  4376.2 1292.63  4396.4 1293.03  4427.6 1288.91  4537.8 1280.30
  4712.7 1275.69  4944.2 1276.15  4972.0 1275.12  4980.1 1270.19  4980.4 1269.69
  4984.1 1270.19  4992.2 1270.35  5012.3 1274.86  5189.1 1278.73  5205.7 1277.75
  5306.7 1282.49  5407.7 1284.16  5594.3 1292.90  5649.8 1296.35  5723.0 1301.59
  5787.6 1309.50  5837.5 1316.50  5845.0 1315.85  5895.5 1320.28  5901.6 1322.45
  6021.5 1338.55  6074.1 1345.77  6139.4 1351.85  6154.2 1353.23  6167.7 1356.93
#Mann=10,-1,0
  4315.6    0.05       0  4944.2    0.12       0  4980.1    0.07       0
  4984.1    0.12       0  5189.1    0.05       0  5594.3    0.12       0
  5649.8    0.05       0  5787.6    0.12       0  6021.5    0.05       0
  6139.4    0.12       0
Bank Sta=4980.1,4984.1
Exp/Cntr=0.3,0.1

Type RM Length L Ch R = 1,6000,1158,1158,1158
BEGIN DESCRIPTION:
ELM HOLLOW CREEK 12.0
END DESCRIPTION:
XS GIS Cut Line= 3
      2812705.68     10202253.12      2812483.78     10203254.53
      2813305.67     10204203.09
#Sta/Elev= 30
  3974.3 1299.76  4015.3 1300.65  4042.2 1297.95  4091.0 1297.18  4127.9 1293.29
  4183.3 1291.44  4226.9 1286.91  4281.6 1285.93  4411.5 1276.09  4537.6 1274.80
  4578.6 1272.47  4639.7 1274.22  4926.6 1272.50  4978.1 1271.88  5005.6 1267.28
  5005.9 1266.78  5009.6 1267.28  5021.9 1270.52  5042.8 1271.86  5120.6 1271.11
  5205.5 1273.34  5268.4 1273.55  5491.5 1276.51  5574.6 1277.82  5681.0 1282.75
  5752.3 1288.68  5908.0 1308.57  5983.8 1314.58  6155.9 1334.83  6255.1 1340.98
#Mann=8,-1,0
  3974.3    0.05       0  4926.6    0.12       0  5005.6    0.07       0
  5009.6    0.12       0  5205.5    0.05       0  5268.4    0.12       0
  5491.5    0.05       0  5983.8    0.12       0
Bank Sta=5005.6,5009.6
Exp/Cntr=0.3,0.1

Type RM Length L Ch R = 1,4842,342,342,342
BEGIN DESCRIPTION:
ELM HOLLOW CREEK 10.0
END DESCRIPTION:
XS GIS Cut Line= 3
      2811405.70     10202853.14      2811766.50     10203404.00
      2812855.65     10204303.08
#Sta/Elev= 30
  4341.5 1282.69  4406.3 1279.24  4421.4 1276.91  4542.8 1268.54  4737.9 1261.43
  4897.5 1259.24  4955.0 1257.34  4970.1 1253.68  4976.1 1254.14  4985.2 1251.29
  4994.6 1251.23  5003.1 1251.02  5003.6 1250.52  5008.7 1251.02  5015.4 1253.92
  5049.0 1257.91  5098.5 1260.48  5298.5 1264.09  5368.8 1264.60  5652.1 1265.33
  5666.5 1266.88  5723.8 1266.63  5971.5 1272.56  6015.1 1275.74  6036.3 1275.13
  6150.5 1280.53  6170.7 1283.05  6191.9 1283.32  6352.3 1300.42  6412.3 1304.84
#Mann=12,-1,0
  4341.5    0.12       0  4542.8    0.05       0  4897.5    0.12       0
  4994.6    0.05       0  5003.1    0.05       0  5008.7    0.05       0
  5015.4    0.12       0  5298.5    0.05       0  5368.8    0.12       0
  6015.1    0.05       0  6150.5    0.12       0  6352.3    0.05       0
Bank Sta=5003.1,5008.7
Exp/Cntr=0.3,0.1

Type RM Length L Ch R = 1,4500,500,500,500
BEGIN DESCRIPTION:
ELM HOLLOW CREEK 9.0
END DESCRIPTION:
XS GIS Cut Line= 3
      2811005.67     10203553.11      2811490.05     10203597.35
      2812639.13     10204338.94
#Sta/Elev= 30
  4513.6 1296.19  4568.7 1293.62  4664.2 1280.32  4720.7 1275.82  4879.0 1263.44
  4955.4 1255.98  4997.2 1248.84  4997.6 1248.34  5002.8 1248.84  5043.3 1255.08
  5073.7 1257.22  5101.9 1255.85  5245.9 1260.61  5305.1 1259.93  5463.7 1257.73
  5478.9 1259.04  5506.6 1256.19  5536.3 1256.65  5551.4 1259.62  5557.4 1256.53
  5587.7 1256.54  5593.7 1258.96  5608.9 1261.10  5768.4 1263.29  5926.3 1269.32
  6065.5 1272.30  6214.1 1280.08  6274.1 1282.21  6346.4 1287.43  6367.6 1288.67
#Mann=9,-1,0
  4513.6    0.12       0  4720.7    0.05       0  4879.0    0.12       0
  4955.4    0.05       0  4997.2    0.05       0  5002.8    0.05       0
  5305.1    0.12       0  6214.1    0.05       0  6346.4    0.12       0
Bank Sta=4997.2,5002.8
Exp/Cntr=0.3,0.1