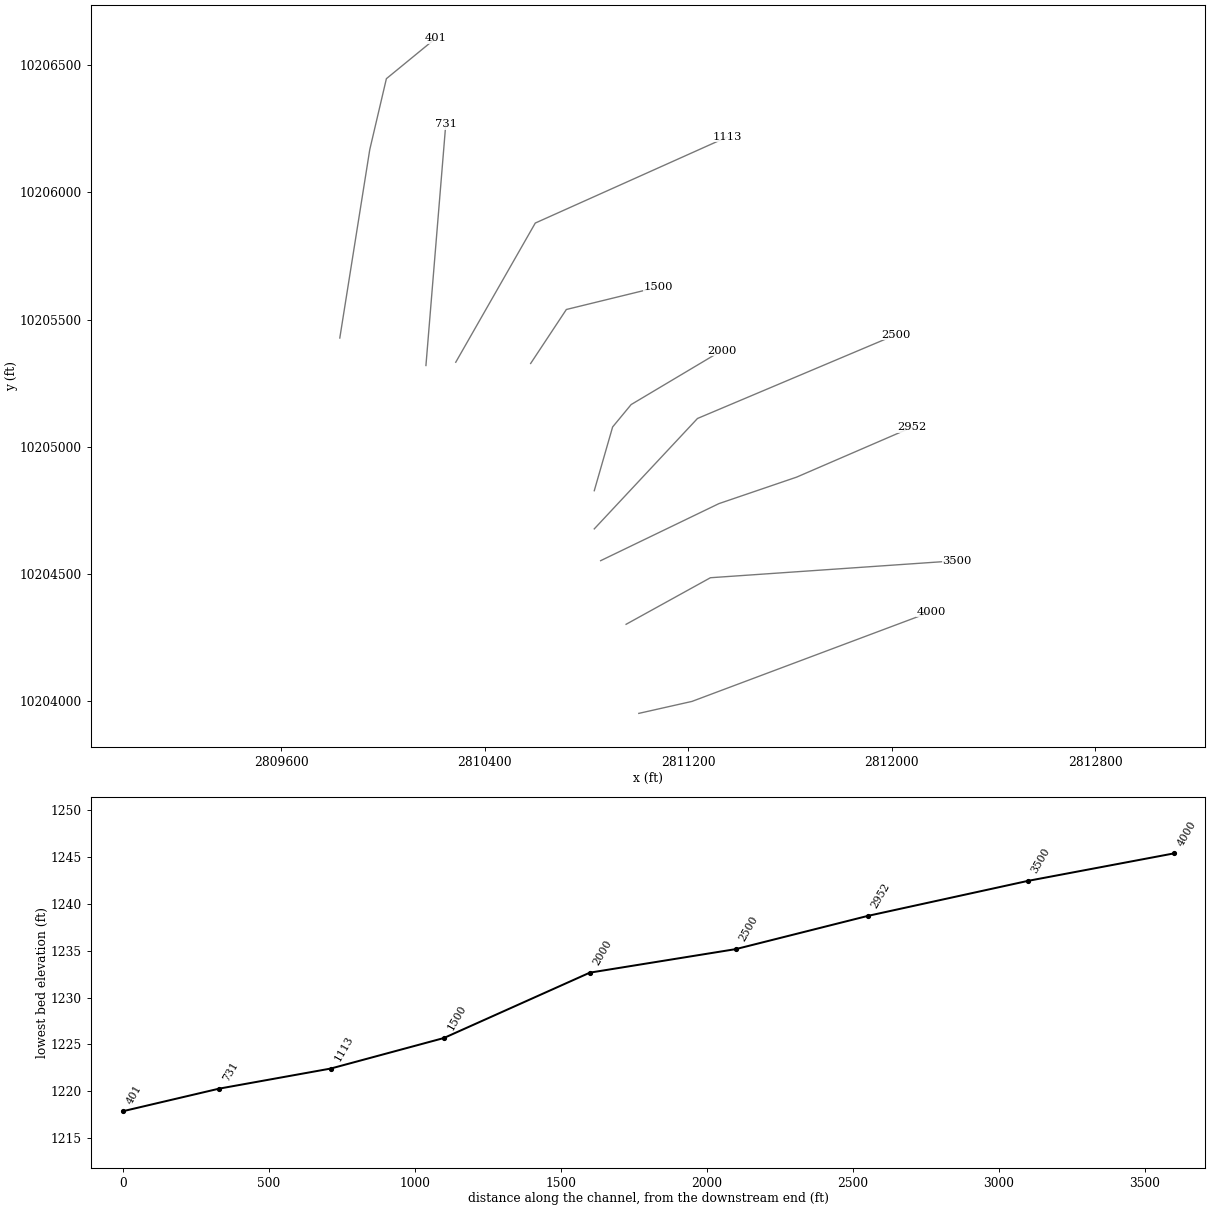
HEC-RAS study ELM HOLLOW CREEK.prj: ELM HOLLOW CREEK Base Level Engineering

--- ELM HOLLOW CREEK.g01 (geometry) --- (continued)

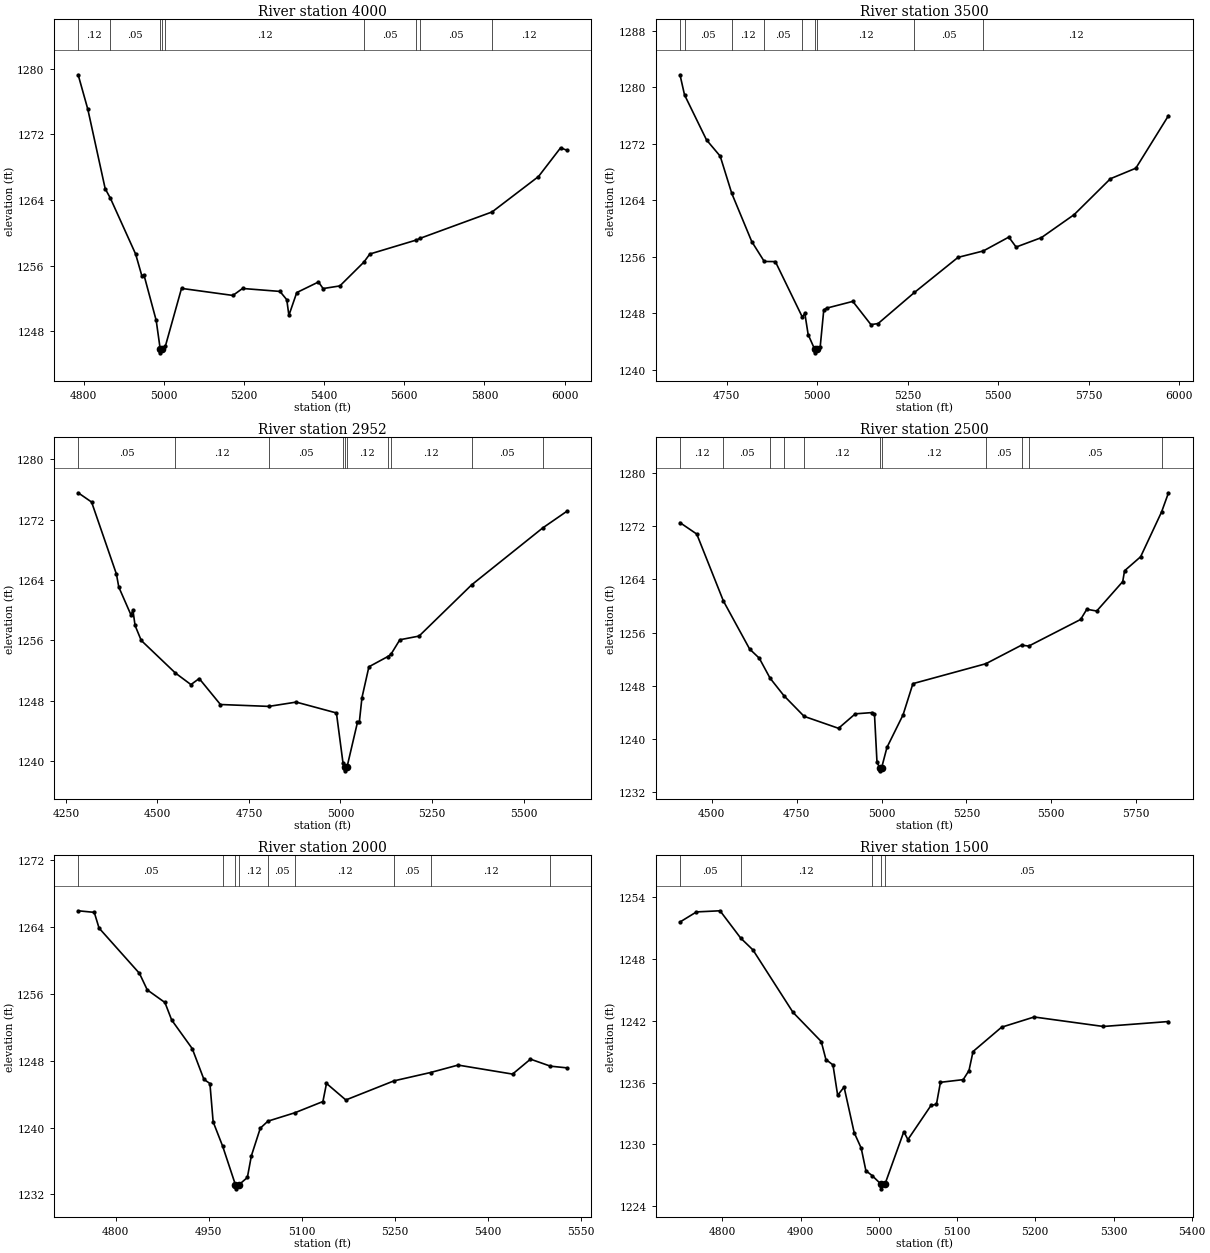
Type RM Length L Ch R = 1,4000,500,500,500
BEGIN DESCRIPTION:
ELM HOLLOW CREEK 8.0
END DESCRIPTION:
XS GIS Cut Line= 3
      2811005.67     10203953.11      2811214.64     10204000.15
      2812155.72     10204353.13
#Sta/Elev= 30
  4785.8 1279.27  4810.0 1275.05  4853.3 1265.37  4866.2 1264.22  4929.3 1257.40
  4944.9 1254.73  4950.1 1254.85  4980.6 1249.31  4990.5 1245.86  4991.0 1245.36
  4996.1 1245.86  5003.6 1246.19  5043.8 1253.22  5172.0 1252.36  5196.1 1253.21
  5289.5 1252.85  5306.5 1251.84  5311.8 1249.93  5331.4 1252.71  5385.6 1254.00
  5397.2 1253.20  5439.0 1253.52  5498.9 1256.42  5513.8 1257.41  5630.1 1259.12
  5639.6 1259.33  5818.9 1262.54  5934.8 1266.86  5989.9 1270.36  6005.1 1270.08
#Mann=9,-1,0
  4785.8    0.12       0  4866.2    0.05       0  4990.5    0.05       0
  4996.1    0.05       0  5003.6    0.12       0  5498.9    0.05       0
  5630.1    0.12       0  5639.6    0.05       0  5818.9    0.12       0
Bank Sta=4990.5,4996.1
Exp/Cntr=0.3,0.1

Type RM Length L Ch R = 1,3500,548,548,548
BEGIN DESCRIPTION:
ELM HOLLOW CREEK 7.0
END DESCRIPTION:
XS GIS Cut Line= 3
      2810955.69     10204303.12      2811287.12     10204486.13
      2812255.71     10204553.11
#Sta/Elev= 30
  4621.4 1281.78  4633.9 1278.94  4694.7 1272.56  4732.5 1270.26  4764.4 1265.00
  4819.6 1258.18  4854.2 1255.36  4884.9 1255.34  4959.1 1247.52  4966.3 1248.00
  4975.5 1245.01  4993.5 1242.93  4994.0 1242.43  4999.2 1242.93  5008.6 1243.21
  5018.6 1248.51  5026.2 1248.75  5098.8 1249.71  5148.9 1246.42  5168.8 1246.58
  5269.2 1250.98  5389.5 1255.94  5459.4 1256.85  5529.8 1258.81  5549.9 1257.40
  5620.0 1258.74  5710.3 1261.99  5810.5 1267.07  5880.7 1268.56  5970.9 1276.00
#Mann=9,-1,0
  4621.4    0.12       0  4633.9    0.05       0  4764.4    0.12       0
  4854.2    0.05       0  4959.1    0.12       0  4993.5    0.07       0
  4999.2    0.12       0  5269.2    0.05       0  5459.4    0.12       0
Bank Sta=4993.5,4999.2
Exp/Cntr=0.3,0.1

Type RM Length L Ch R = 1,2952,452,452,452
BEGIN DESCRIPTION:
ELM HOLLOW CREEK 6.0
END DESCRIPTION:
XS GIS Cut Line= 4
      2810855.70     10204553.12      2811320.46     10204777.37
      2811626.02     10204881.54      2812080.69     10205078.11
#Sta/Elev= 30
  4283.5 1275.55  4320.2 1274.32  4388.0 1264.78  4394.5 1263.05  4427.7 1259.37
  4433.2 1259.97  4438.9 1257.97  4455.8 1255.98  4548.9 1251.67  4591.5 1250.13
  4614.1 1250.93  4672.1 1247.49  4804.1 1247.24  4879.0 1247.81  4988.9 1246.37
  5006.9 1239.72  5012.0 1239.20  5012.5 1238.70  5017.8 1239.20  5046.3 1245.12
  5051.5 1245.19  5058.6 1248.39  5077.6 1252.49  5129.0 1253.84  5137.7 1254.14
  5162.1 1256.07  5214.6 1256.56  5358.2 1263.35  5552.3 1270.89  5617.7 1273.08
#Mann=10,-1,0
  4283.5    0.05       0  4548.9    0.12       0  4804.1    0.05       0
  5006.9    0.12       0  5012.0    0.05       0  5017.8    0.12       0
  5129.0    0.05       0  5137.7    0.12       0  5358.2    0.05       0
  5552.3    0.12       0
Bank Sta=5012,5017.8
Exp/Cntr=0.3,0.1

Type RM Length L Ch R = 1,2500,500,500,500
BEGIN DESCRIPTION:
ELM HOLLOW CREEK 5.0
END DESCRIPTION:
XS GIS Cut Line= 3
      2810830.67     10204678.10      2811236.25     10205111.95
      2812014.94     10205440.58
#Sta/Elev= 30
  4406.1 1272.56  4455.5 1270.84  4534.0 1260.75  4611.3 1253.51  4639.6 1252.14
  4671.4 1249.13  4712.2 1246.49  4771.8 1243.37  4873.1 1241.57  4922.5 1243.75
  4972.3 1243.94  4979.1 1243.66  4986.5 1236.42  4994.4 1235.66  4994.9 1235.16
  5000.3 1235.66  5015.8 1238.69  5063.2 1243.59  5092.3 1248.30  5307.1 1251.30
  5412.3 1254.10  5433.5 1253.96  5586.3 1257.97  5604.6 1259.51  5633.7 1259.24
  5710.3 1263.67  5715.8 1265.31  5763.1 1267.42  5824.8 1274.17  5845.2 1277.06
#Mann=11,-1,0
  4406.1    0.12       0  4534.0    0.05       0  4671.4    0.12       0
  4712.2    0.05       0  4771.8    0.12       0  4994.4    0.07       0
  5000.3    0.12       0  5307.1    0.05       0  5412.3    0.12       0
  5433.5    0.05       0  5824.8    0.12       0
Bank Sta=4994.4,5000.3
Exp/Cntr=0.3,0.1

Type RM Length L Ch R = 1,2000,500,500,500
BEGIN DESCRIPTION:
ELM HOLLOW CREEK 4.0
END DESCRIPTION:
XS GIS Cut Line= 4
      2810830.68     10204828.10      2810902.75     10205078.54
      2810975.54     10205166.63      2811330.67     10205378.10
#Sta/Elev= 30
  4739.4 1265.97  4765.4 1265.78  4773.1 1263.90  4838.3 1258.47  4850.9 1256.49
  4879.4 1254.98  4890.3 1252.88  4923.5 1249.45  4942.3 1245.77  4952.0 1245.27
  4957.2 1240.68  4972.5 1237.77  4993.1 1233.15  4993.6 1232.65  4999.0 1233.15
  5012.4 1234.01  5018.9 1236.61  5033.3 1239.92  5045.6 1240.76  5089.2 1241.77
  5134.3 1243.11  5140.1 1245.28  5171.3 1243.30  5249.0 1245.59  5308.0 1246.59
  5352.4 1247.48  5440.3 1246.40  5469.2 1248.19  5501.4 1247.35  5527.6 1247.15
#Mann=9,-1,0
  4739.4    0.05       0  4972.5    0.12       0  4993.1    0.07       0
  4999.0    0.12       0  5045.6    0.05       0  5089.2    0.12       0
  5249.0    0.05       0  5308.0    0.12       0  5501.4    0.05       0
Bank Sta=4993.1,4999
Exp/Cntr=0.3,0.1

Type RM Length L Ch R = 1,1500,387,387,387
BEGIN DESCRIPTION:
ELM HOLLOW CREEK 3.0
END DESCRIPTION:
XS GIS Cut Line= 3
      2810580.68     10205328.11      2810720.97     10205540.21
      2811080.68     10205628.11
#Sta/Elev= 30
  4745.7 1251.58  4766.8 1252.56  4796.9 1252.67  4823.3 1250.02  4839.0 1248.87
  4890.2 1242.81  4926.3 1239.98  4932.3 1238.23  4941.3 1237.71  4947.3 1234.76
  4955.5 1235.56  4968.4 1231.14  4977.4 1229.63  4983.4 1227.44  4991.3 1226.97
  5002.1 1226.18  5002.6 1225.68  5008.0 1226.18  5031.9 1231.23  5037.1 1230.46
  5066.6 1233.77  5073.6 1233.89  5078.7 1236.02  5107.8 1236.28  5115.2 1237.16
  5120.4 1239.01  5156.9 1241.37  5198.5 1242.36  5287.0 1241.44  5370.3 1241.92
#Mann=5,-1,0
  4745.7    0.05       0  4823.3    0.12       0  4991.3    0.05       0
  5002.1    0.05       0  5008.0    0.05       0
Bank Sta=5002.1,5008
Exp/Cntr=0.3,0.1

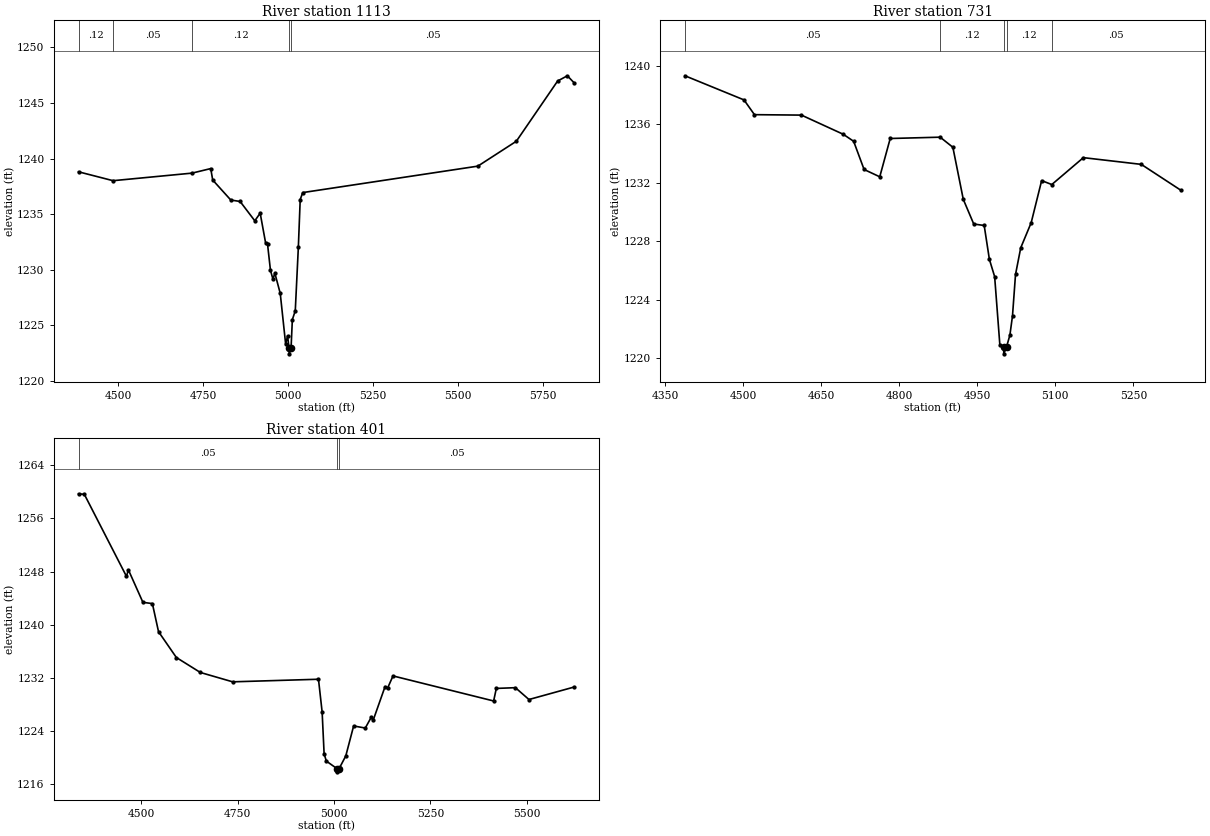
Type RM Length L Ch R = 1,1113,382,382,382
BEGIN DESCRIPTION:
Mapping XS a01b1ae9
END DESCRIPTION:
XS GIS Cut Line= 3
      2810286.36     10205333.02      2810598.87     10205879.91
      2811354.08     10206218.46
#Sta/Elev= 30
  4384.2 1238.81  4485.8 1238.01  4717.9 1238.69  4773.0 1239.10  4778.8 1238.07
  4832.0 1236.27  4859.4 1236.14  4902.6 1234.40  4918.4 1235.09  4934.3 1232.42
  4940.0 1232.31  4948.7 1229.93  4955.8 1229.17  4961.6 1229.68  4977.4 1227.87
  4993.3 1223.30  4999.0 1224.05  5003.3 1222.93  5003.8 1222.43  5009.2 1222.93
  5013.0 1225.51  5021.6 1226.30  5030.6 1232.00  5036.1 1236.31  5043.5 1236.94
  5558.5 1239.32  5671.7 1241.56  5793.1 1246.98  5821.7 1247.45  5841.7 1246.81
#Mann=5,-1,0
  4384.2    0.12       0  4485.8    0.05       0  4717.9    0.12       0
  5003.3    0.07       0  5009.2    0.05       0
Bank Sta=5003.3,5009.2
Exp/Cntr=0.3,0.1

Type RM Length L Ch R = 1,731,330,330,330
BEGIN DESCRIPTION:
Mapping XS 7ff2881b
END DESCRIPTION:
XS GIS Cut Line= 2
      2810169.18     10205320.06      2810247.21     10206269.36
#Sta/Elev= 30
  4388.4 1239.31  4501.8 1237.66  4521.9 1236.65  4612.2 1236.62  4692.5 1235.31
  4712.5 1234.83  4732.6 1232.90  4762.7 1232.40  4782.8 1235.02  4878.8 1235.11
  4903.2 1234.42  4923.2 1230.86  4943.3 1229.17  4963.4 1229.07  4973.4 1226.75
  4983.5 1225.57  4993.5 1220.90  5000.6 1220.79  5001.1 1220.29  5006.5 1220.79
  5012.8 1221.57  5017.8 1222.89  5023.6 1225.72  5033.6 1227.54  5053.7 1229.26
  5073.8 1232.14  5093.3 1231.87  5154.0 1233.71  5265.3 1233.25  5340.9 1231.49
#Mann=5,-1,0
  4388.4    0.05       0  4878.8    0.12       0  5000.6    0.07       0
  5006.5    0.12       0  5093.3    0.05       0
Bank Sta=5000.6,5006.5
Exp/Cntr=0.3,0.1

Type RM Length L Ch R = 1,401,0,0,0
BEGIN DESCRIPTION:
ELM HOLLOW CREEK 1.0
END DESCRIPTION:
XS GIS Cut Line= 4
      2809830.68     10205428.11      2809948.42     10206168.37
      2810013.77     10206447.20      2810207.38     10206605.76
#Sta/Elev= 30
  4336.7 1259.71  4351.9 1259.62  4461.1 1247.29  4466.2 1248.26  4503.8 1243.38
  4528.4 1243.19  4544.3 1238.97  4590.6 1235.08  4652.8 1232.83  4736.7 1231.42
  4959.4 1231.81  4968.9 1226.88  4974.0 1220.62  4979.7 1219.50  5007.0 1218.38
  5007.5 1217.88  5013.1 1218.38  5030.3 1220.28  5050.6 1224.78  5080.9 1224.47
  5096.2 1226.08  5101.4 1225.65  5132.2 1230.71  5138.7 1230.47  5152.8 1232.31
  5413.9 1228.54  5420.9 1230.43  5470.4 1230.54  5505.6 1228.76  5622.9 1230.64
#Mann=3,-1,0
  4336.7    0.05       0  5007.0    0.03       0  5013.1    0.05       0
Bank Sta=5007,5013.1
Exp/Cntr=0.3,0.1

Chan Stop Cuts=-1