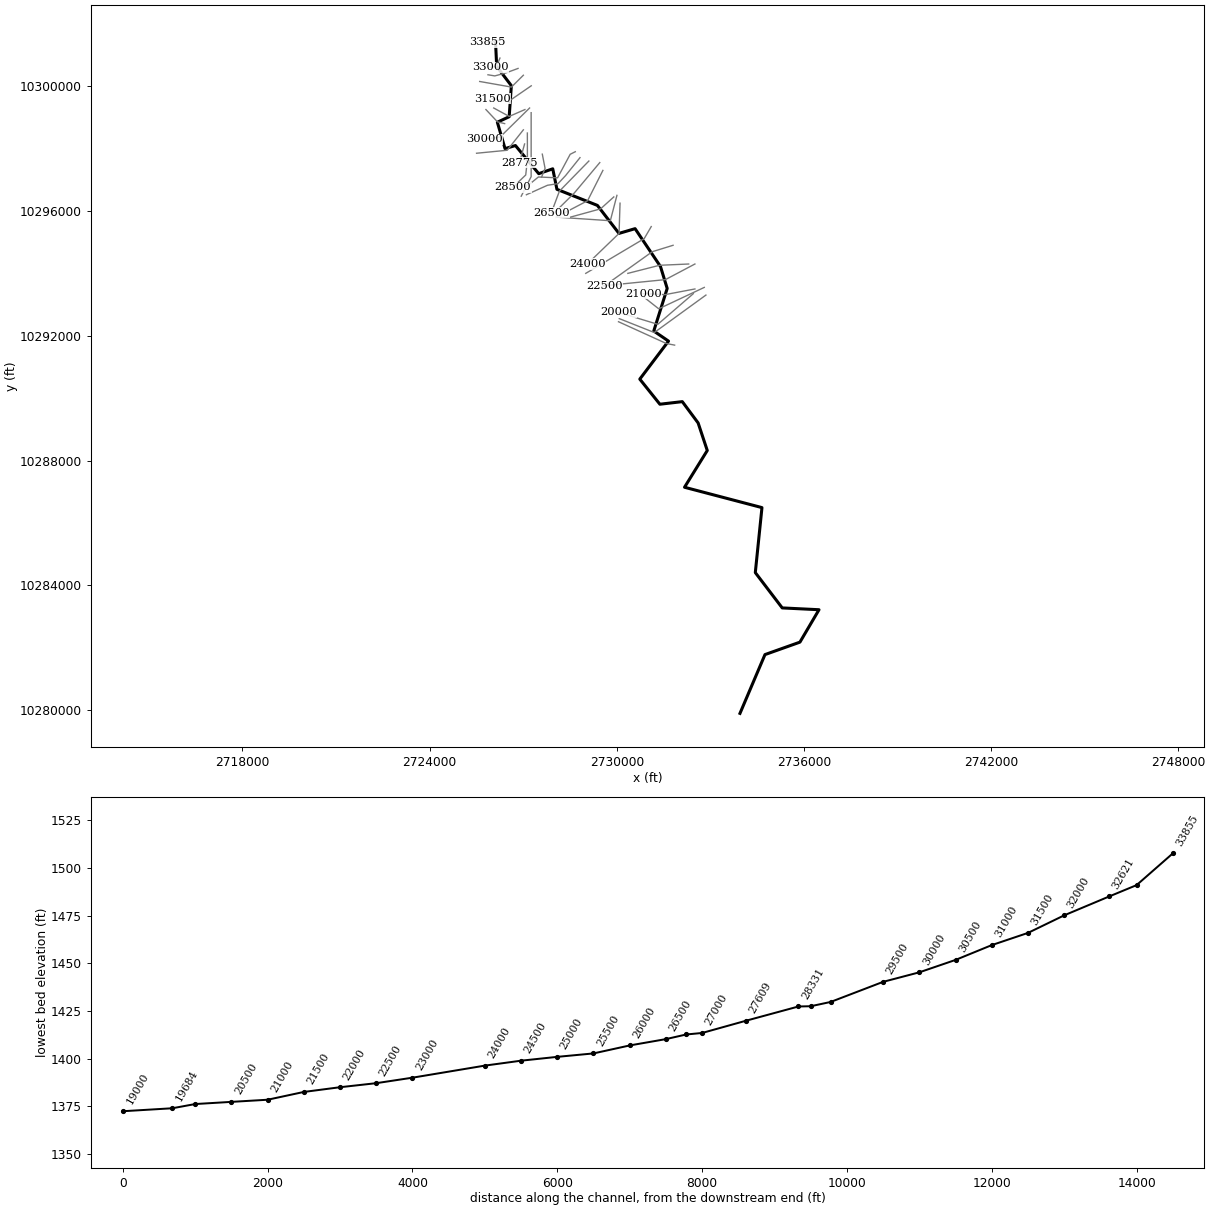
--- FIELD CREEK.prj (project) ---

Proj Title=FIELD CREEK Base Level Engineering
Current Plan=p01
Default Exp/Contr=0.3,0.1
English Units
Geom File=g01
Flow File=f01
Plan File=p01
Y Axis Title=Elevation
X Axis Title(PF)=Main Channel Distance
X Axis Title(XS)=Station
BEGIN DESCRIPTION:
FIELD CREEK
END DESCRIPTION:
DSS Export Rating Curves= 0
DSS Export Rating Curve Sorted= 0
DSS Export Volume Flow Curves= 0
DXF OffsetX= 0
DXF OffsetY= 0
DXF ScaleX= 1
DXF ScaleY= 10

--- FIELD CREEK.p01 (plan) ---

Plan Title=Multiple Run
Short Identifier=Multiple
Geom File=g01
Flow File=f01
Subcritical Flow
K Sum by GR= 0
Std Step Tol= 0.01
Critical Tol= 0.01
Num of Std Step Trials= 20
Max Error Tol= 0.3
Flow Tol Ratio= 0.001
Split Flow NTrial= 30
Split Flow Tol= 0.02
Split Flow Ratio= 0.02
Log Output Level= 0
Friction Slope Method= 1
Unsteady Friction Slope Method= 2
Unsteady Bridges Friction Slope Method= 1
Parabolic Critical Depth
Global Vel Dist=  1 , 1 , 1
Global Log Level= 0
CheckData=True
Encroach Param= -1, 0, 0, 0
BEGIN DESCRIPTION:
Multiple Run
END DESCRIPTION:

--- FIELD CREEK.f01 (steady flow) ---

Flow Title=Multiple
Program Version=4.10
Number of Profiles= 7
Profile Names=10-year,25-year,50-year,1pct_min,100-year,1pct_plu,500-year
River Rch & RM=FIELD CREEK,Reach-1         ,33855
     722    1218    2442    1830    3494    6672    5097
River Rch & RM=FIELD CREEK,Reach-1         ,27000
    1180    2041    4447    3081    6474   13601    9362
River Rch & RM=FIELD CREEK,Reach-1         ,23000
    1967    3494    8104    7251   11993   19836   17181
River Rch & RM=FIELD CREEK,Reach-1         ,17000
    6255   11912   21639   16525   31587   60377   42985
River Rch & RM=FIELD CREEK,Reach-1         ,10000
    6997   13341   23702   18886   34529   63130   46767
River Rch & RM=FIELD CREEK,Reach-1         ,4500
    6844   13048   23106   17156   33682   66126   45649
Boundary for River Rch & Prof#=FIELD CREEK,Reach-1         , 1
Up Type= 0
Dn Type= 3
Dn Slope=0.005
Boundary for River Rch & Prof#=FIELD CREEK,Reach-1         , 2
Up Type= 0
Dn Type= 3
Dn Slope=0.005
Boundary for River Rch & Prof#=FIELD CREEK,Reach-1         , 3
Up Type= 0
Dn Type= 3
Dn Slope=0.005
Boundary for River Rch & Prof#=FIELD CREEK,Reach-1         , 4
Up Type= 0
Dn Type= 3
Dn Slope=0.005
Boundary for River Rch & Prof#=FIELD CREEK,Reach-1         , 5
Up Type= 0
Dn Type= 3
Dn Slope=0.005
Boundary for River Rch & Prof#=FIELD CREEK,Reach-1         , 6
Up Type= 0
Dn Type= 3
Dn Slope=0.005
Boundary for River Rch & Prof#=FIELD CREEK,Reach-1         , 7
Up Type= 0
Dn Type= 3
Dn Slope=0.005
DSS Import GetInterval= 0
DSS Import GetPeak= 0
DSS Import FillOption= 0

--- FIELD CREEK.g01 (geometry) ---

Geom Title=Existing Conditions
Program Version=4.10

River Reach=FIELD CREEK     ,Reach-1
Reach XY= 30
      2726112.75       10301438.        2726151.       10300636.
        2726621.       10300019.        2726551.       10299023.
        2726172.       10298847.      2726418.25       10298001.
      2726752.25       10298100.      2727498.75       10297198.
        2727948.       10297354.      2728082.25       10296697.
        2729380.       10296181.        2730071.       10295284.
       2730587.5       10295436.      2731401.75       10294223.
        2731617.       10293520.       2731186.5       10292155.
        2731659.       10291832.       2730738.5       10290614.
       2731382.5       10289809.      2732101.25       10289892.
      2732608.25       10289210.      2732901.75       10288326.
       2732172.5       10287148.        2734655.       10286496.
       2734441.5       10284413.       2735304.5       10283281.
        2736484.       10283223.      2735872.25       10282184.
       2734751.5       10281785.      2733950.25       10279901.

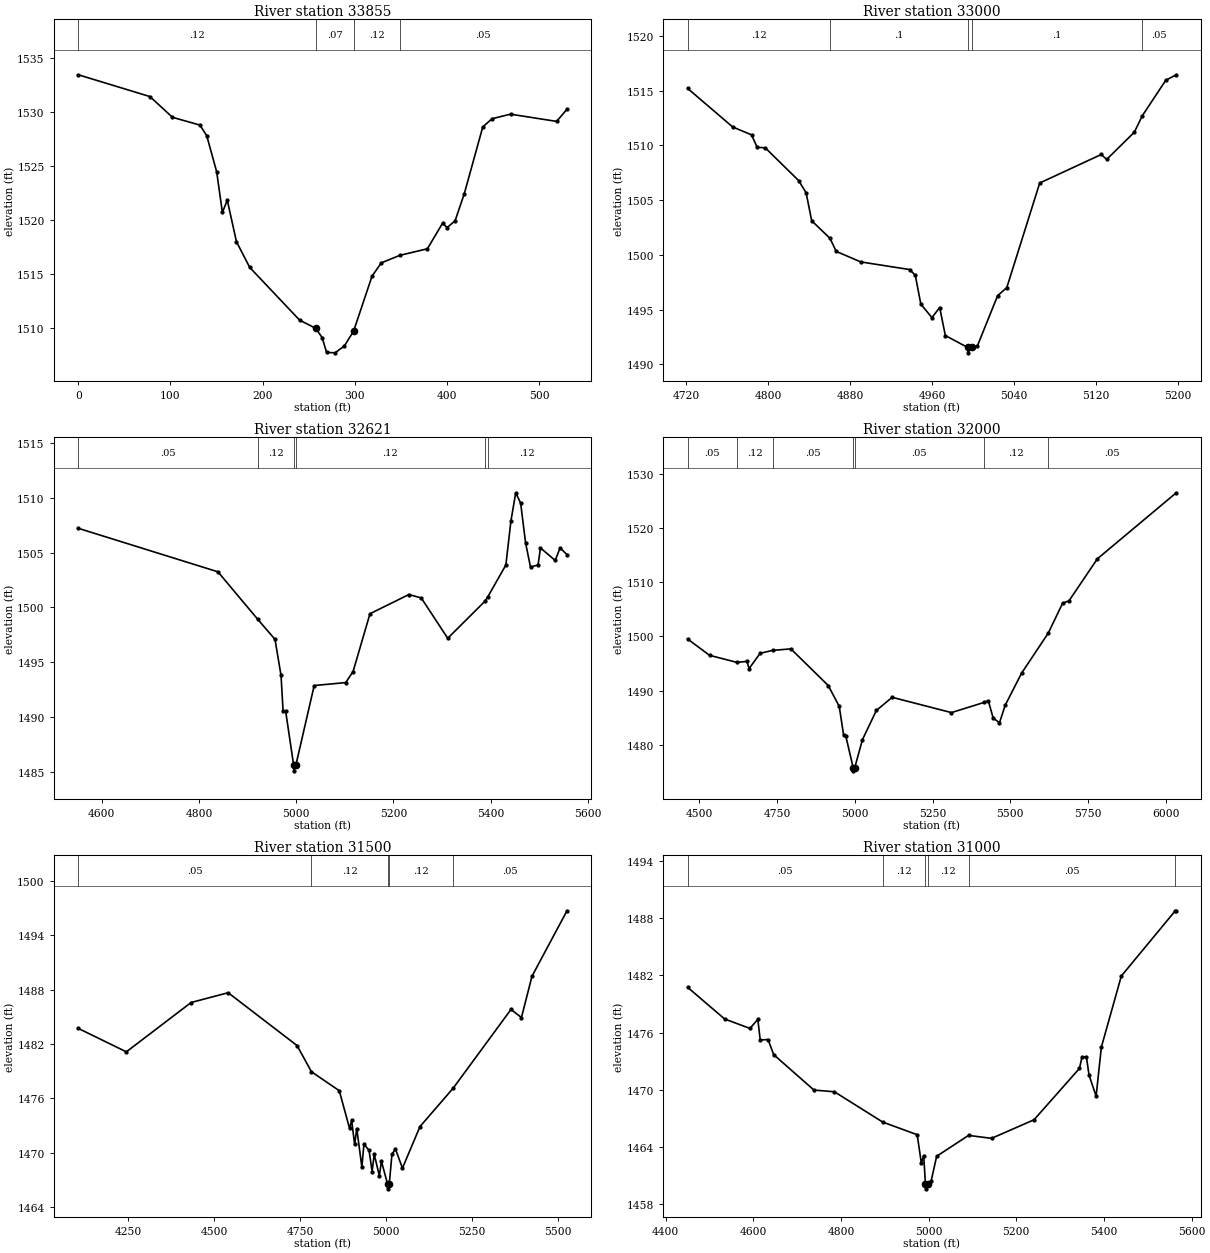
Type RM Length L Ch R = 1 ,33855   ,500,500,500
BEGIN DESCRIPTION:
FIELD CREEK 64.0
END DESCRIPTION:
XS GIS Cut Line= 3
      2726365.39     10301535.77      2726111.69     10301435.72
      2725854.49     10301419.91
#Sta/Elev= 30
       0 1533.44    77.8 1531.42   102.2  1529.5     132 1528.78   139.4  1527.8
   150.2 1524.45   156.4 1520.69   161.7 1521.82   171.7 1517.97   186.1 1515.59
   240.2 1510.71   257.7 1509.95   264.6  1509.1   269.5 1507.72   278.7 1507.68
   288.8 1508.32   298.8 1509.69   318.8 1514.78   328.8 1516.01   348.9 1516.71
   378.9 1517.32   395.3 1519.68   400.4 1519.29     409 1519.92     419 1522.44
     439 1528.61   449.1 1529.37   469.1 1529.79   519.2 1529.12   530.4 1530.25
#Mann= 4 ,-1 , 0
       0     .12       0   257.7     .07       0   298.8     .12       0
   348.9     .05       0
Bank Sta=257.7,298.8
XS Rating Curve= 0 ,0
Exp/Cntr=0.3,0.1

Type RM Length L Ch R = 1 ,33000   ,379,379,379
BEGIN DESCRIPTION:
FIELD CREEK 63.0
END DESCRIPTION:
XS GIS Cut Line= 3
      2726255.69     10300903.12      2726149.12     10300646.04
      2725955.72     10300603.12
#Sta/Elev= 30
  4721.7 1515.22  4765.7 1511.69  4784.1 1510.97  4789.5 1509.84  4797.5 1509.78
    4830 1506.79  4837.3 1505.67  4842.7 1503.12  4860.6 1501.51  4866.6 1500.32
  4890.5 1499.36  4938.2 1498.66  4943.7 1498.14  4949.1  1495.5  4959.9 1494.27
  4967.5 1495.19    4973 1492.63  4994.6 1491.55  4994.9 1491.05    4999 1491.55
  5004.3  1491.7    5024 1496.28  5032.9 1497.01    5065 1506.57  5125.1 1509.18
  5130.2 1508.72  5157.2 1511.21  5165.1 1512.73  5187.9 1515.96  5198.1 1516.46
#Mann= 5 ,-1 , 0
  4721.7     .12       0  4860.6      .1       0  4994.6     .07       0
    4999      .1       0  5165.1     .05       0
Bank Sta=4994.6,4999
XS Rating Curve= 0 ,0
Exp/Cntr=0.3,0.1

Type RM Length L Ch R = 1 ,32621   ,621,621,621
BEGIN DESCRIPTION:
Mapping XS cb00e5f1
END DESCRIPTION:
XS GIS Cut Line= 4
       2726835.2     10300570.99      2726439.36     10300425.15
       2726090.4      10300331.4       2725871.7     10300367.86
#Sta/Elev= 30
  4551.9 1507.22  4839.1 1503.25  4921.1 1498.91  4956.4 1497.09  4968.8  1493.8
    4973 1490.57  4978.2 1490.57  4994.8  1485.6  4995.1  1485.1  4999.2  1485.6
    5037 1492.88  5101.8 1493.15  5116.9 1494.15  5151.7 1499.43  5231.7 1501.18
  5257.1 1500.87  5311.6 1497.19  5387.7 1500.55  5393.8 1500.96  5431.1 1503.87
  5441.5 1507.88  5451.4 1510.46  5461.5 1509.52  5471.7 1505.88  5481.8 1503.68
  5497.3 1503.88  5502.3 1505.43  5532.5 1504.29  5542.6 1505.43  5556.8 1504.82
#Mann= 6 ,-1 , 0
  4551.9     .05       0  4921.1     .12       0  4994.8     .07       0
  4999.2     .12       0  5387.7     .05       0  5393.8     .12       0
Bank Sta=4994.8,4999.2
XS Rating Curve= 0 ,0
Exp/Cntr=0.3,0.1

Type RM Length L Ch R = 1 ,32000   ,500,500,500
BEGIN DESCRIPTION:
FIELD CREEK 62.0
END DESCRIPTION:
XS GIS Cut Line= 3
      2727005.69     10300353.11      2726623.75     10299973.78
      2725605.72      10300153.1
#Sta/Elev= 30
  4461.7 1499.54  4532.4 1496.52  4620.3 1495.22  4652.6  1495.4  4659.7 1494.08
  4695.1 1496.89  4735.1 1497.43    4794 1497.71  4914.2 1490.95  4949.6  1487.1
  4963.8 1481.75  4970.8  1481.6  4994.7  1475.7    4995  1475.2  4999.1  1475.7
  5024.2 1480.95  5069.1 1486.35  5119.9 1488.77  5310.5 1485.95  5415.1 1487.82
    5429 1488.17  5444.8 1484.94  5465.1 1484.07  5483.2 1487.28  5536.2 1493.23
  5622.1 1500.63  5668.2 1506.15  5688.5 1506.56  5779.9 1514.33  6033.7 1526.52
#Mann= 7 ,-1 , 0
  4461.7     .05       0  4620.3     .12       0  4735.1     .05       0
  4994.7     .03       0  4999.1     .05       0  5415.1     .12       0
  5622.1     .05       0
Bank Sta=4994.7,4999.1
XS Rating Curve= 0 ,0
Exp/Cntr=0.3,0.1

Type RM Length L Ch R = 1 ,31500   ,500,500,500
BEGIN DESCRIPTION:
FIELD CREEK 61.0
END DESCRIPTION:
XS GIS Cut Line= 3
       2727259.1     10300014.92      2726522.22     10299508.37
      2726005.64     10299603.12
#Sta/Elev= 30
  4105.8 1483.72  4245.4 1481.13  4433.5 1486.58  4541.1 1487.66  4741.3 1481.82
    4783 1478.93  4863.8 1476.84  4893.6 1472.69  4899.7 1473.55  4908.5  1470.9
  4914.6 1472.66  4929.4 1468.42  4935.5 1470.94  4950.4 1470.24  4959.2  1467.9
  4965.3 1469.83  4980.2 1467.44  4986.3 1469.04  5004.3  1466.5  5004.6    1466
    5009  1466.5  5016.8 1469.81    5027  1470.4  5047.3 1468.28  5098.1 1472.87
  5194.5 1477.11  5362.5 1485.81    5393 1484.92  5423.5 1489.48  5525.2 1496.71
#Mann= 5 ,-1 , 0
  4105.8     .05       0    4783     .12       0  5004.3     .07       0
    5009     .12       0  5194.5     .05       0
Bank Sta=5004.3,5009
XS Rating Curve= 0 ,0
Exp/Cntr=0.3,0.1

Type RM Length L Ch R = 1 ,31000   ,500,500,500
BEGIN DESCRIPTION:
FIELD CREEK 60.0
END DESCRIPTION:
XS GIS Cut Line= 3
      2727055.65      10299253.1      2726551.81     10299033.03
      2726055.67     10299303.12
#Sta/Elev= 30
  4450.2 1480.76  4534.8 1477.43  4592.5 1476.44  4610.5 1477.39  4615.9 1475.23
  4633.9 1475.27  4646.6 1473.69  4738.4 1469.97  4785.2 1469.79  4895.3 1466.61
    4974 1465.28  4983.4 1462.31  4988.8 1463.09  4992.8  1460.1  4993.1  1459.6
  4997.6  1460.1    5006 1460.46  5018.4 1463.02  5091.1 1465.21  5143.6  1464.9
  5240.5 1466.85  5344.1 1472.24  5349.8 1473.42  5359.9 1473.47  5365.9 1471.55
  5382.1 1469.33  5394.1 1474.48  5439.6 1481.94  5562.7 1488.79  5564.9 1488.79
#Mann= 6 ,-1 , 0
  4450.2     .05       0  4895.3     .12       0  4992.8     .07       0
  4997.6     .12       0  5091.1     .05       0  5562.7     .12       0
Bank Sta=4992.8,4997.6
XS Rating Curve= 0 ,0
Exp/Cntr=0.3,0.1

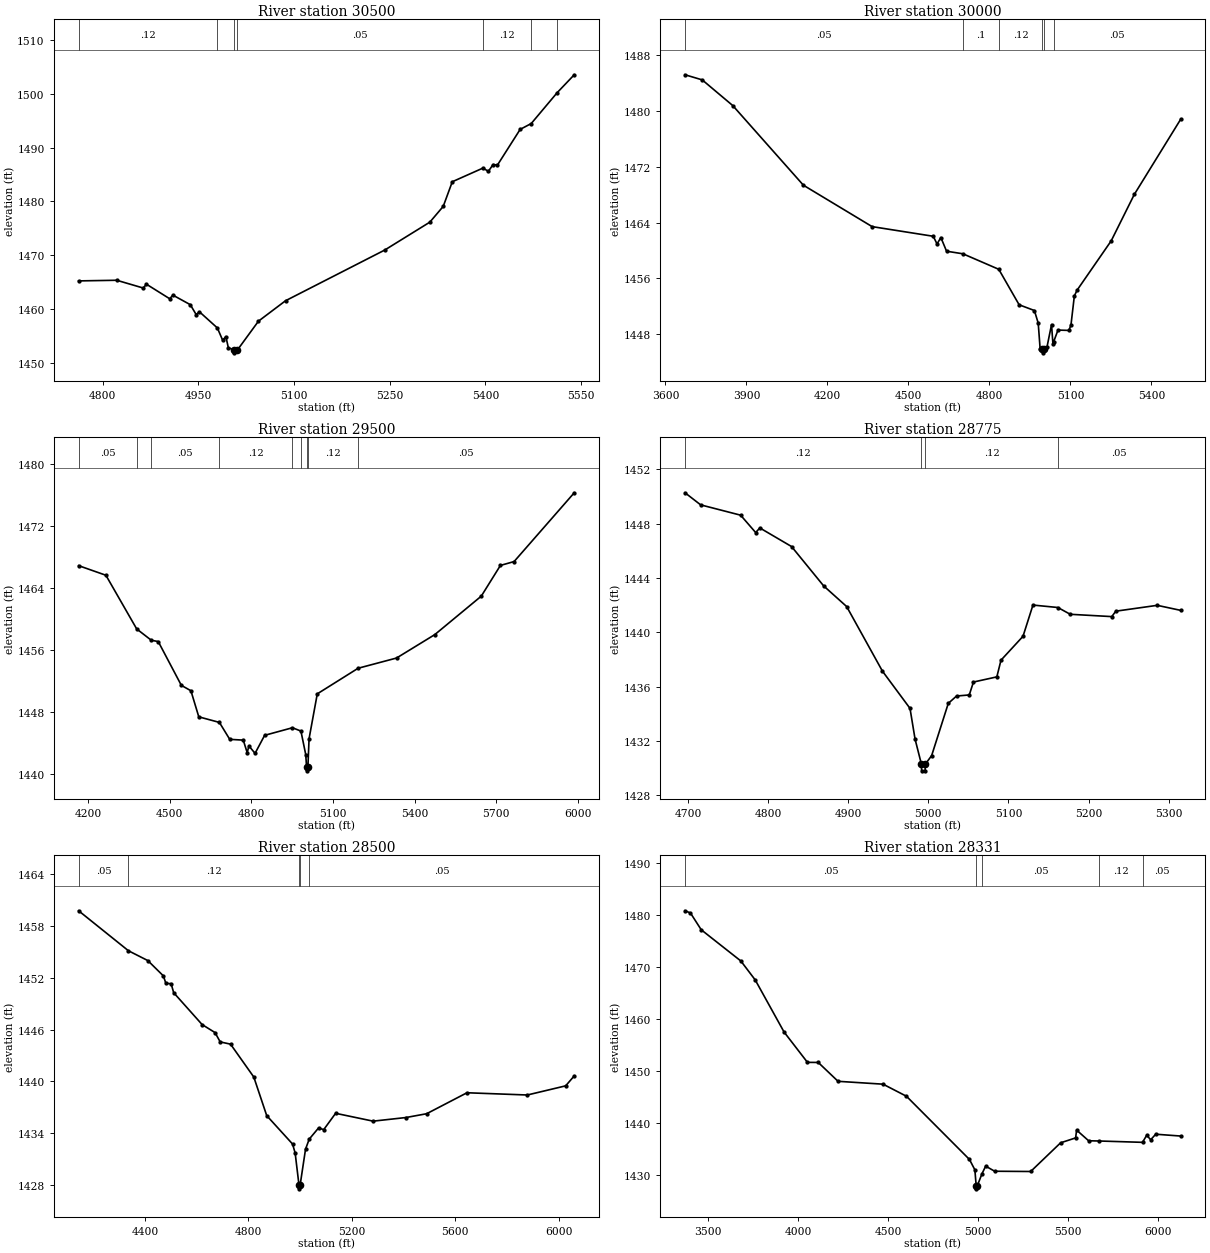
Type RM Length L Ch R = 1 ,30500   ,500,500,500
BEGIN DESCRIPTION:
FIELD CREEK 59.0
END DESCRIPTION:
XS GIS Cut Line= 3
       2726405.7     10298803.11      2726174.89     10298859.93
      2725805.66     10299253.14
#Sta/Elev= 30
  4762.3 1465.21    4822 1465.33  4863.5 1463.89  4868.7 1464.59    4905  1461.9
  4910.2 1462.56  4937.4 1460.79  4946.6 1458.95  4951.7 1459.47  4979.8 1456.47
  4988.1 1454.19  4993.2 1454.86    4997 1452.81  5006.3 1452.34  5006.6 1451.84
  5011.1 1452.34  5044.3 1457.73  5086.7 1461.52  5242.2 1470.94    5313 1476.13
    5334 1479.06  5348.2 1483.64  5396.3 1486.18  5404.8 1485.57  5412.1 1486.83
    5419 1486.74  5454.6 1493.37    5472 1494.46  5512.7  1500.2  5539.4 1503.52
#Mann= 7 ,-1 , 0
  4762.3     .12       0  4979.8     .05       0  5006.3     .05       0
  5011.1     .05       0  5396.3     .12       0    5472     .05       0
  5512.7     .12       0
Bank Sta=5006.3,5011.1
XS Rating Curve= 0 ,0
Exp/Cntr=0.3,0.1

Type RM Length L Ch R = 1 ,30000   ,500,500,500
BEGIN DESCRIPTION:
FIELD CREEK 58.0
END DESCRIPTION:
XS GIS Cut Line= 3
      2727205.68     10299303.11      2726259.11     10298372.39
      2725755.65     10298303.11
#Sta/Elev= 30
  3672.5 1485.15  3736.1 1484.42  3849.3 1480.74  4110.9 1469.34  4365.5 1463.41
  4591.8 1462.03  4605.9 1460.93  4620.1 1461.85  4641.2 1459.89  4701.8 1459.52
  4834.6  1457.3    4910 1452.22  4966.5  1451.4  4980.7 1449.59  4987.8  1445.9
  4996.4 1445.84  4996.8 1445.34  5001.3 1445.84  5013.5 1446.23    5030 1449.39
  5035.1 1446.66  5037.7 1446.91  5053.9  1448.6  5094.3 1448.55    5102 1449.33
  5114.5 1453.48  5124.6 1454.31  5251.1 1461.38  5336.6 1468.02  5508.2 1478.77
#Mann= 6 ,-1 , 0
  3672.5     .05       0  4701.8      .1       0  4834.6     .12       0
  4996.4     .07       0  5001.3     .12       0  5037.7     .05       0
Bank Sta=4996.4,5001.3
XS Rating Curve= 0 ,0
Exp/Cntr=0.3,0.1

Type RM Length L Ch R = 1 ,29500   ,725,725,725
BEGIN DESCRIPTION:
FIELD CREEK 57.0
END DESCRIPTION:
XS GIS Cut Line= 3
       2727005.7     10298603.13      2726487.86     10297948.48
      2725505.68     10297853.11
#Sta/Elev= 30
  4165.3 1466.87  4265.5 1465.63  4378.7 1458.69  4432.3 1457.23  4457.9 1457.06
  4542.8  1451.4    4578  1450.7  4606.9 1447.33  4682.6 1446.61  4720.7 1444.42
  4770.4 1444.32  4784.8  1442.7  4791.2 1443.57  4813.7 1442.61  4848.9 1444.94
  4951.1 1445.92  4982.3 1445.49    5000 1442.45    5003 1440.85  5003.4 1440.35
    5008 1440.85  5012.2  1444.5  5042.4  1450.3  5192.5 1453.61  5333.7 1454.93
  5474.4 1457.96  5645.2 1462.93  5715.5  1466.9  5765.8  1467.4  5986.8 1476.29
#Mann= 9 ,-1 , 0
  4165.3     .05       0  4378.7     .12       0  4432.3     .05       0
  4682.6     .12       0  4951.1     .05       0  4982.3     .12       0
    5003     .07       0    5008     .12       0  5192.5     .05       0
Bank Sta=5003,5008
XS Rating Curve= 0 ,0
Exp/Cntr=0.3,0.1

Type RM Length L Ch R = 1 ,28775   ,275,275,275
BEGIN DESCRIPTION:
FIELD CREEK 56.0
END DESCRIPTION:
XS GIS Cut Line= 3
        2727045.     10298149.99      2726931.25     10297737.03
      2726895.01     10297550.05
#Sta/Elev= 30
  4696.2 1450.28  4715.7 1449.39  4765.6 1448.63  4784.4 1447.35  4789.6 1447.69
  4829.2 1446.32  4869.3 1443.42    4898  1441.9  4942.7 1437.14  4977.1  1434.4
  4983.4 1432.14  4991.3  1430.3  4991.6  1429.8  4995.9  1429.8  4996.3  1430.3
  5004.1 1430.92  5024.9 1434.77  5035.2 1435.31  5051.1 1435.39  5056.3 1436.34
  5085.5 1436.72  5090.7 1437.95  5118.2 1439.71  5130.6 1442.01  5161.7 1441.83
  5177.2 1441.33    5229 1441.16  5234.1 1441.56  5285.8 1441.99    5315 1441.62
#Mann= 4 ,-1 , 0
  4696.2     .12       0  4991.3     .07       0  4996.3     .12       0
  5161.7     .05       0
Bank Sta=4991.3,4996.3
XS Rating Curve= 0 ,0
Exp/Cntr=0.3,0.1

Type RM Length L Ch R = 1 ,28500   ,169,169,169
BEGIN DESCRIPTION:
FIELD CREEK 55.0
END DESCRIPTION:
XS GIS Cut Line= 4
      2727134.08     10298500.94      2727135.89     10297643.94
      2727081.88     10297156.58      2726670.62     10296761.39
#Sta/Elev= 30
    4143 1459.77  4335.7 1455.14  4410.8    1454  4470.8 1452.23  4480.8 1451.35
  4500.8 1451.33  4510.8 1450.28  4620.8 1446.59  4670.8 1445.66  4690.8 1444.58
  4730.8 1444.32  4820.8 1440.51  4870.8 1436.04  4970.8 1432.75  4980.8 1431.71
  4995.4 1428.06  4995.8 1427.56  5000.4 1428.06    5021 1432.16  5035.3 1433.32
  5071.3 1434.61  5091.4 1434.42  5137.4 1436.31  5282.5  1435.4  5409.4 1435.82
  5489.6 1436.26  5645.7 1438.69  5879.1 1438.43  6027.5 1439.49  6060.7 1440.64
#Mann= 5 ,-1 , 0
    4143     .05       0  4335.7     .12       0  4995.4     .07       0
  5000.4     .12       0  5035.3     .05       0
Bank Sta=4995.4,5000.4
XS Rating Curve= 0 ,0
Exp/Cntr=0.3,0.1

Type RM Length L Ch R = 1 ,28331   ,722,722,722
BEGIN DESCRIPTION:
FIELD CREEK 54.0
END DESCRIPTION:
XS GIS Cut Line= 3
      2727255.68     10299153.15      2727255.68     10297103.11
      2726937.01     10296476.52
#Sta/Elev= 30
  3371.5 1480.83  3401.5 1480.41  3461.5 1477.18  3681.5 1471.19  3761.5 1467.54
  3921.5 1457.55  4051.5 1451.72  4111.5  1451.7  4221.5 1448.08  4471.5 1447.53
  4601.5 1445.21  4951.5 1433.07  4981.5 1431.08    4989 1427.93  4989.4 1427.43
    4994 1427.93  5021.5 1430.36  5041.5 1431.79  5091.5 1430.81  5291.5 1430.76
  5457.7 1436.27  5541.1 1437.21  5546.7 1438.71  5613.5 1436.66  5669.7 1436.62
  5912.8 1436.36    5936 1437.72  5958.2 1436.86  5986.1 1437.92  6124.5 1437.57
#Mann= 5 ,-1 , 0
  3371.5     .05       0    4989     .05       0  5021.5     .05       0
  5669.7     .12       0  5912.8     .05       0
Bank Sta=4989,4994
XS Rating Curve= 0 ,0
Exp/Cntr=0.3,0.1

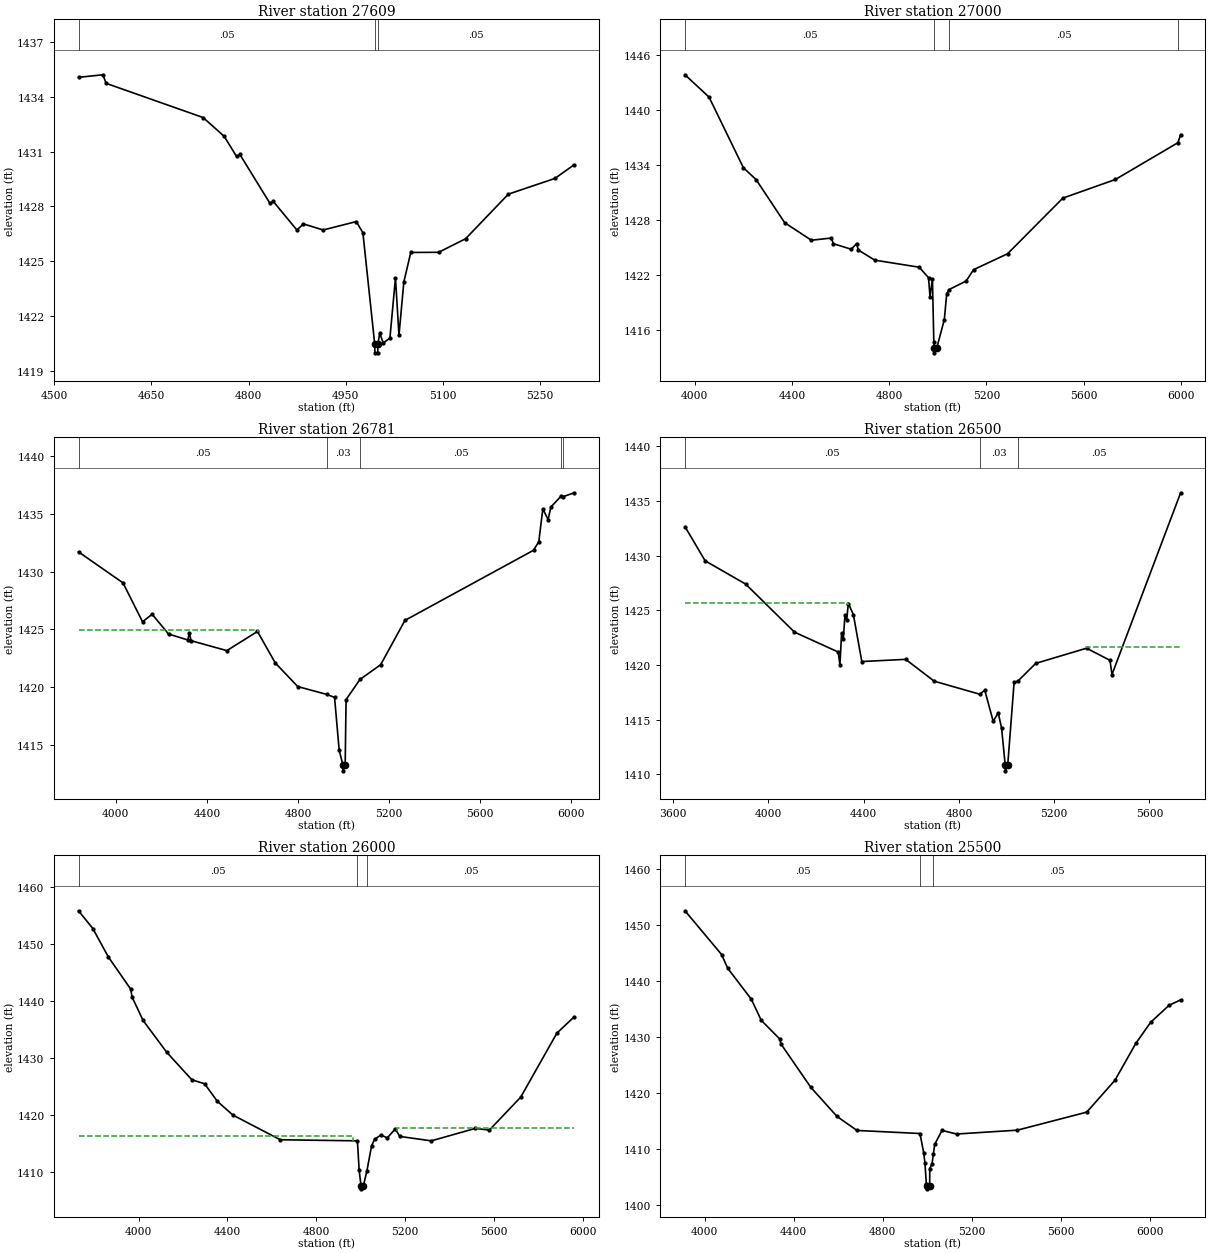
Type RM Length L Ch R = 1 ,27609   ,609,609,609
BEGIN DESCRIPTION:
FIELD CREEK 53.0
END DESCRIPTION:
XS GIS Cut Line= 3
      2727613.24     10297823.85      2727701.75       10297370.
      2727590.48      10297088.6
#Sta/Elev= 30
  4537.6 1435.06  4575.2  1435.2  4580.3 1434.73    4730 1432.86  4762.5 1431.83
  4781.6 1430.73  4786.7 1430.84  4833.2 1428.16  4838.3 1428.27  4874.6 1426.71
  4884.8 1427.04  4915.3 1426.71  4966.3 1427.17  4976.5 1426.56  4994.7 1420.49
  4995.1 1419.99  4999.4 1419.99  4999.8 1420.49  5002.5 1421.08  5007.8 1420.53
  5018.2 1420.79  5026.8 1424.09  5032.2 1420.95  5039.7 1423.86  5050.4 1425.48
  5093.4 1425.49    5135 1426.23    5201 1428.67  5272.9 1429.53  5302.6 1430.28
#Mann= 3 ,-1 , 0
  4537.6     .05       0  4994.7     .05       0  4999.8     .05       0
Bank Sta=4994.7,4999.8
XS Rating Curve= 0 ,0
Exp/Cntr=0.3,0.1

Type RM Length L Ch R = 1 ,27000   ,219,219,219
BEGIN DESCRIPTION:
FIELD CREEK 52.0
END DESCRIPTION:
XS GIS Cut Line= 5
       2728670.5     10297901.92      2728507.24     10297819.59
      2728102.34     10297064.78      2727488.39     10297092.58
      2727191.34     10296849.83
#Sta/Elev= 30
  3960.6 1443.84  4059.5 1441.41  4200.7 1433.71  4252.9 1432.42  4370.5 1427.72
  4480.1 1425.81  4562.1 1426.05  4570.7 1425.43  4644.2 1424.83  4666.1 1425.44
  4672.8 1424.75  4740.9 1423.64  4923.5 1422.87  4961.7 1421.73  4967.9 1419.67
  4977.9 1421.57  4983.6 1414.67  4985.7 1414.04  4986.2 1413.54  4995.4 1414.04
  5026.7 1417.16  5036.7    1420  5046.7 1420.44  5116.8 1421.37  5146.8  1422.6
  5286.9 1424.34    5514  1430.4  5730.1 1432.43  5987.1 1436.44  5998.2 1437.32
#Mann= 4 ,-1 , 0
  3960.6     .05       0  4985.7     .05       0  5046.7     .05       0
  5987.1     .12       0
Bank Sta=4985.7,4995.4
XS Rating Curve= 0 ,0
Exp/Cntr=0.3,0.1

Type RM Length L Ch R = 1 ,26781   ,281,281,281
BEGIN DESCRIPTION:
Mapping XS 6867a910
END DESCRIPTION:
XS GIS Cut Line= 5
      2728821.34     10297712.21      2728361.26     10297139.28
       2728118.2     10296878.86      2727779.66     10296826.78
      2727102.55     10296522.94
#Sta/Elev= 30
  3836.6 1431.71  4031.8 1429.03  4117.6 1425.66  4159.8 1426.31  4231.8  1424.6
  4316.6 1424.08    4323  1424.7    4331 1424.02  4487.8 1423.16    4622 1424.82
  4700.1  1422.1  4798.8 1420.05  4925.8 1419.37  4960.5 1419.11  4980.8 1414.54
  4997.3 1413.25  4997.8 1412.75  5007.1 1413.25  5011.1 1418.92  5071.8 1420.66
  5162.9 1421.94  5269.6 1425.78  5833.8 1431.85    5857 1432.59  5874.7 1435.43
  5897.9 1434.51  5910.2  1435.6  5956.5 1436.57  5962.1 1436.48  6012.3 1436.83
#Mann= 5 ,-1 , 0
  3836.6     .05       0  4925.8     .03       0  5071.8     .05       0
  5956.5     .12       0  5962.1     .05       0
#XS Ineff= 2 , 0
          4623.3 1424.93 5242.83         1424.53
Permanent Ineff=
       F       F
Bank Sta=4997.3,5007.1
XS Rating Curve= 0 ,0
Exp/Cntr=0.3,0.1

Type RM Length L Ch R = 1 ,26500   ,500,500,500
BEGIN DESCRIPTION:
FIELD CREEK 51.0
END DESCRIPTION:
XS GIS Cut Line= 3
      2729105.71     10297603.14      2728161.82     10296637.68
      2727905.69     10295953.13
#Sta/Elev= 30
  3649.8 1432.66  3734.6 1429.53  3904.4 1427.41  4109.5 1423.01  4293.3 1421.19
  4300.4 1420.01  4307.4 1422.93  4314.6 1422.39  4321.6 1424.59  4328.7 1424.11
  4335.7 1425.63    4357  1424.6  4392.3 1420.32  4576.2 1420.52  4696.5 1418.52
  4887.4 1417.33  4908.5  1417.7  4943.9 1414.85  4965.1 1415.63  4979.2 1414.21
  4994.5 1410.82    4995 1410.32  5004.8 1410.82  5031.7 1418.41  5047.6 1418.53
  5122.5 1420.15  5335.9 1421.54  5434.3 1420.43  5442.6 1419.13  5730.9 1435.76
#Mann= 3 ,-1 , 0
  3649.8     .05       0  4887.4     .03       0  5047.6     .05       0
#XS Ineff= 2 , 0
         4335.23 1425.64 5335.23         1421.66
Permanent Ineff=
       F       F
Bank Sta=4994.5,5004.8
XS Rating Curve= 0 ,0
Exp/Cntr=0.3,0.1

Type RM Length L Ch R = 1 ,26000   ,500,500,500
BEGIN DESCRIPTION:
FIELD CREEK 50.0
END DESCRIPTION:
XS GIS Cut Line= 3
      2729455.68     10297553.11      2728639.11     10296579.38
      2727955.66     10295903.09
#Sta/Elev= 30
  3729.2 1455.78  3793.6 1452.67  3863.9 1447.66    3964 1442.05  3970.5 1440.64
    4020 1436.54  4126.6 1430.95  4239.8 1426.13  4297.1 1425.43  4354.3 1422.36
  4424.6 1419.94  4637.9 1415.61  4985.3 1415.42  4993.1 1410.29  5001.6  1407.5
  5002.1    1407    5012  1407.5  5028.1 1410.16  5049.3 1414.59  5063.4 1415.73
  5091.7 1416.44    5120 1415.94  5155.4  1417.5  5176.5 1416.19    5318 1415.42
    5516  1417.6  5579.6 1417.31  5721.1  1423.1  5883.7 1434.32  5961.5 1437.16
#Mann= 3 ,-1 , 0
  3729.2     .05       0  4985.3     .03       0  5028.1     .05       0
#XS Ineff= 2 , 0
         4965.52 1416.25 5161.44         1417.65
Permanent Ineff=
       F       F
Bank Sta=5001.6,5012
XS Rating Curve= 0 ,0
Exp/Cntr=0.3,0.1

Type RM Length L Ch R = 1 ,25500   ,500,500,500
BEGIN DESCRIPTION:
FIELD CREEK 49.0
END DESCRIPTION:
XS GIS Cut Line= 3
      2729555.67     10297303.08      2729064.98     10296331.45
       2728055.7     10295803.12
#Sta/Elev= 30
  3911.5 1452.48  4075.9 1444.67  4103.8  1442.2  4209.6 1436.69  4254.2 1432.92
  4337.2 1429.59  4343.4 1428.66  4477.2 1420.94  4594.8 1415.75  4684.5 1413.25
  4967.6  1412.7  4984.3 1409.29  4989.9 1407.52  4996.3 1403.67  5000.8 1403.32
  5001.3 1402.82  5011.2 1403.32  5011.7 1406.43  5021.8 1407.28  5028.1 1409.06
  5033.7 1410.75  5066.6 1413.25  5132.8 1412.61  5405.5  1413.3  5717.4 1416.52
  5844.1 1422.22    5938 1428.81  6004.2 1432.55  6086.9 1435.59  6139.2 1436.57
#Mann= 3 ,-1 , 0
  3911.5     .05       0  4967.6     .03       0  5028.1     .05       0
Bank Sta=5000.8,5011.2
XS Rating Curve= 0 ,0
Exp/Cntr=0.3,0.1

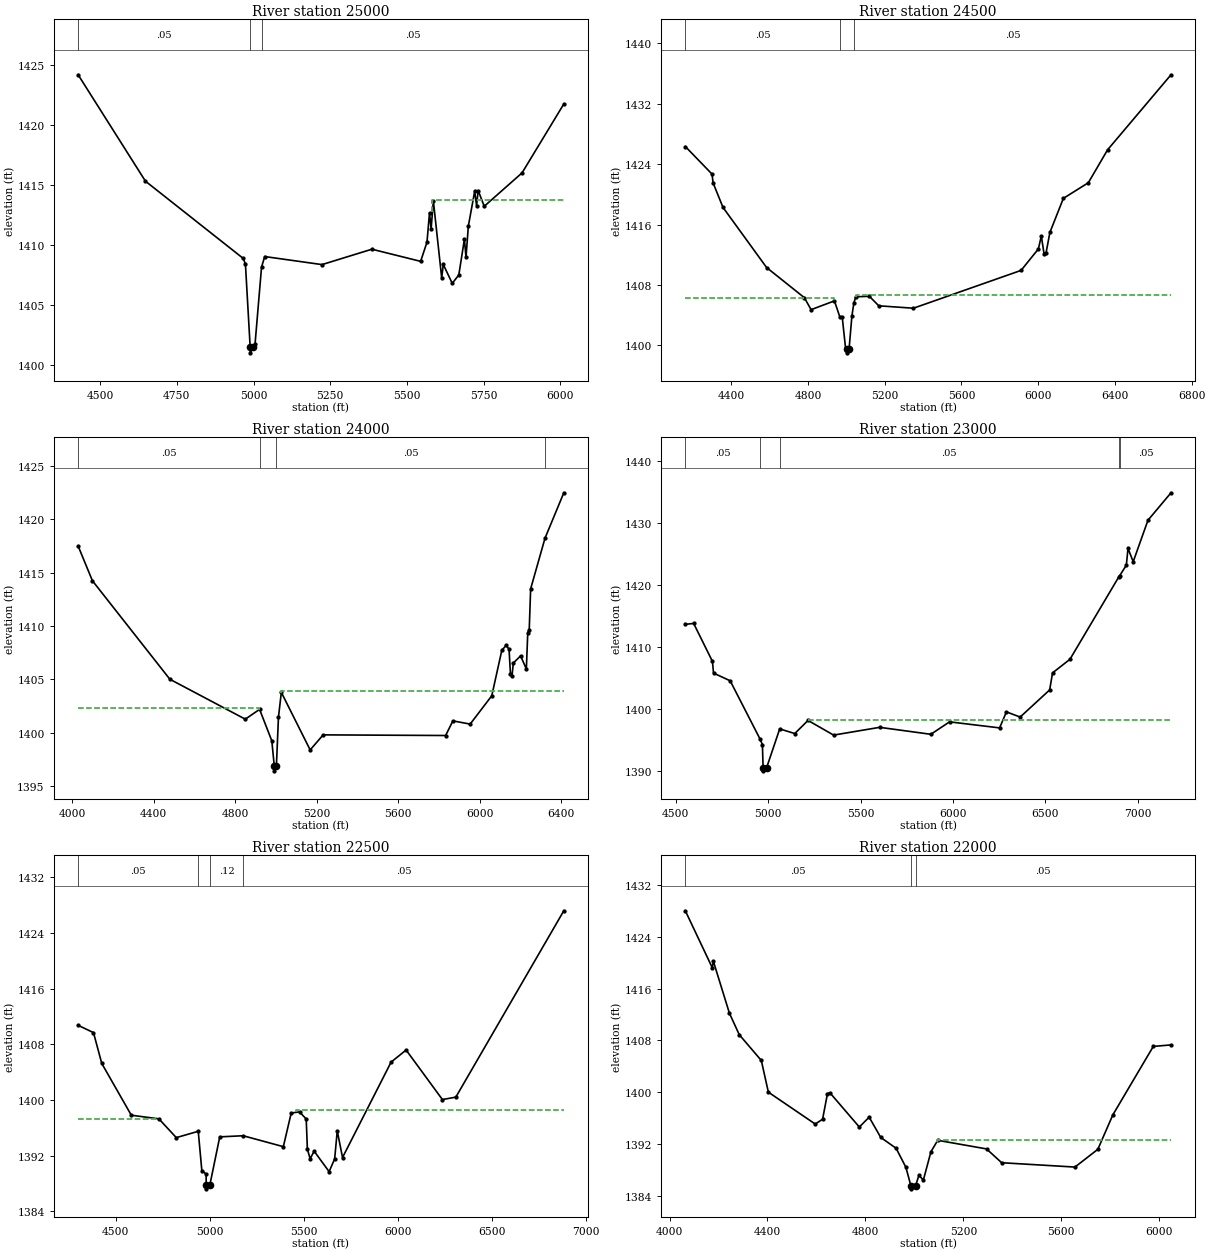
Type RM Length L Ch R = 1 ,25000   ,500,500,500
BEGIN DESCRIPTION:
FIELD CREEK 48.0
END DESCRIPTION:
XS GIS Cut Line= 3
      2729905.66     10296453.09      2729480.92     10296070.72
      2728505.67     10295803.11
#Sta/Elev= 30
  4428.5 1424.15  4647.8  1415.3  4966.7 1408.87  4973.7  1408.4  4989.1 1401.52
  4989.6 1401.02  4999.8 1401.52    5005 1401.74  5026.2 1408.15  5036.5 1409.03
  5223.2 1408.36  5385.8 1409.64  5544.7 1408.63  5565.4 1410.23  5573.6 1412.68
  5578.8 1411.31  5586.1 1413.67  5613.3 1407.26  5618.5 1408.37  5647.7  1406.8
  5669.1  1407.5  5687.4 1410.48  5692.5 1408.96  5700.2 1411.57  5720.9 1414.47
    5727 1413.27  5732.2 1414.52    5752 1413.21  5875.2 1415.99  6011.3 1421.72
#Mann= 3 ,-1 , 0
  4428.5     .05       0  4989.1     .03       0  5026.2     .05       0
#XS Ineff= 2 , 0
                          5583.3         1413.72
Permanent Ineff=
       F       F
Bank Sta=4989.1,4999.8
XS Rating Curve= 0 ,0
Exp/Cntr=0.3,0.1

Type RM Length L Ch R = 1 ,24500   ,500,500,500
BEGIN DESCRIPTION:
FIELD CREEK 47.0
END DESCRIPTION:
XS GIS Cut Line= 3
      2730005.69     10296503.15      2729794.23     10295690.41
      2728105.68     10295803.11
#Sta/Elev= 30
  4160.2 1426.34  4299.5 1422.68  4304.9 1421.52  4356.6 1418.27  4583.9 1410.31
  4780.6 1406.32  4815.9 1404.73  4937.5 1405.89  4966.2 1403.73    4978  1403.8
    4996 1399.53  5003.2 1399.51  5003.7 1399.01  5013.9 1399.51  5028.6 1403.87
  5038.6 1405.58  5048.6 1406.43  5119.7  1406.5  5168.9 1405.24  5349.3 1404.92
  5910.6 1409.93  6000.8 1412.77  6016.2 1414.48  6030.8 1412.07  6040.9 1412.25
  6060.9 1414.96  6131.1 1419.47  6261.3 1421.54  6361.6  1425.9  6692.3 1435.84
#Mann= 3 ,-1 , 0
  4160.2     .05       0  4966.2     .03       0  5038.6     .05       0
#XS Ineff= 2 , 0
         4934.09 1406.25  5048.3         1406.64
Permanent Ineff=
       F       F
Bank Sta=5003.2,5013.9
XS Rating Curve= 0 ,0
Exp/Cntr=0.3,0.1

Type RM Length L Ch R = 1 ,24000   ,1000,1000,1000
BEGIN DESCRIPTION:
FIELD CREEK 46.0
END DESCRIPTION:
XS GIS Cut Line= 3
      2730105.68      10296253.1       2730073.8     10295283.72
      2729055.66     10294303.09
#Sta/Elev= 30
  4030.1 1417.49  4100.1 1414.24  4480.3 1405.01  4850.5 1401.27  4920.6 1402.19
  4980.6 1399.24  4992.4 1396.93  4992.9 1396.43  5003.2 1396.93  5013.2 1401.46
  5027.3 1403.78  5168.8 1398.39  5232.6  1399.8  5833.6 1399.74  5869.1 1401.11
    5954 1400.81    6060 1403.46  6109.3 1407.72  6130.7 1408.19  6144.9 1407.82
  6151.8 1405.49    6159 1405.27  6165.9 1406.53  6201.5  1407.2  6229.8 1405.97
  6236.7 1409.38  6243.9 1409.67  6250.8 1413.48  6321.2 1418.22  6413.6 1422.48
#Mann= 4 ,-1 , 0
  4030.1     .05       0  4920.6     .03       0  5003.2     .05       0
  6321.2     .12       0
#XS Ineff= 2 , 0
         4917.61 1402.31 5026.99         1403.89
Permanent Ineff=
       F       F
Bank Sta=4992.4,5003.2
XS Rating Curve= 0 ,0
Exp/Cntr=0.3,0.1

Type RM Length L Ch R = 1 ,23000   ,500,500,500
BEGIN DESCRIPTION:
FIELD CREEK 44.0
END DESCRIPTION:
XS GIS Cut Line= 3
      2731105.69     10295503.12      2730879.54      10295116.4
       2729005.7     10294003.12
#Sta/Elev= 30
    4552 1413.67    4597 1413.82  4698.7 1407.71  4704.5 1405.83  4794.6 1404.59
  4954.9 1395.29  4969.1 1394.33  4972.7  1390.6  4973.2  1390.1  4991.7  1390.6
  5062.6 1396.85  5144.1  1396.1  5215.8 1398.21  5354.2 1395.85  5603.5  1397.1
  5880.2 1395.98  5981.5 1397.98  6252.3 1397.01  6289.3 1399.59  6363.4 1398.75
  6523.1 1403.12  6538.7 1405.86  6632.9 1408.05  6897.7 1421.33  6902.7 1421.53
    6938 1423.19    6947 1425.89  6975.1 1423.75  7054.9 1430.42  7179.6 1434.84
#Mann= 5 ,-1 , 0
    4552     .05       0  4954.9     .03       0  5062.6     .05       0
  6897.7     .12       0  6902.7     .05       0
#XS Ineff= 2 , 0
                         5215.91         1398.25
Permanent Ineff=
       F       F
Bank Sta=4972.7,4991.7
XS Rating Curve= 0 ,0
Exp/Cntr=0.3,0.1

Type RM Length L Ch R = 1 ,22500   ,500,500,500
BEGIN DESCRIPTION:
FIELD CREEK 43.0
END DESCRIPTION:
XS GIS Cut Line= 3
      2731805.67     10294903.11      2731137.78     10294696.88
      2729605.65     10293603.09
#Sta/Elev= 30
    4301 1410.72  4382.6 1409.67  4426.6 1405.24  4583.6  1397.8  4730.1 1397.28
  4822.7 1394.58  4939.4 1395.49  4958.5 1389.85  4981.3 1389.34  4981.7 1387.72
  4982.2 1387.22  5000.7 1387.72  5053.7 1394.69  5178.1 1394.85  5391.7 1393.28
  5433.5 1398.11  5477.7 1398.28  5513.3 1397.25  5519.5 1392.91  5534.2 1391.55
  5555.5 1392.63    5635 1389.69  5664.5 1391.53  5678.3 1395.55  5706.3 1391.72
  5964.4 1405.43  6044.3 1407.17  6237.2 1400.05  6308.5  1400.4  6882.5 1427.18
#Mann= 4 ,-1 , 0
    4301     .05       0  4939.4     .05       0  5000.7     .12       0
  5178.1     .05       0
#XS Ineff= 2 , 0
         4729.55 1397.31 5459.09         1398.62
Permanent Ineff=
       F       F
Bank Sta=4981.7,5000.7
XS Rating Curve= 0 ,0
Exp/Cntr=0.3,0.1

Type RM Length L Ch R = 1 ,22000   ,500,500,500
BEGIN DESCRIPTION:
FIELD CREEK 42.0
END DESCRIPTION:
XS GIS Cut Line= 3
      2732305.65     10294303.11      2731371.14     10294262.21
      2730355.67     10294003.11
#Sta/Elev= 30
  4064.6 1428.01  4174.3 1419.25  4179.3 1420.19  4244.7  1412.2  4284.8 1408.89
  4374.9 1404.91  4403.7 1400.02  4595.1  1395.1  4625.1 1395.84  4645.1  1399.8
  4655.1 1399.92  4775.2 1394.64  4815.3 1396.16  4862.7 1393.03  4925.4 1391.36
  4965.4 1388.42  4985.5  1385.6    4986  1385.1    5005  1385.6  5018.8  1387.2
  5036.6 1386.44  5067.6 1390.82  5095.4 1392.59  5294.6 1391.26  5356.5 1389.13
  5655.8 1388.46  5749.2  1391.2  5810.6 1396.52  5975.7 1407.08    6048 1407.31
#Mann= 3 ,-1 , 0
  4064.6     .05       0  4985.5     .05       0    5005     .05       0
#XS Ineff= 2 , 0
                         5092.33         1392.56
Permanent Ineff=
       F       F
Bank Sta=4985.5,5005
XS Rating Curve= 0 ,0
Exp/Cntr=0.3,0.1

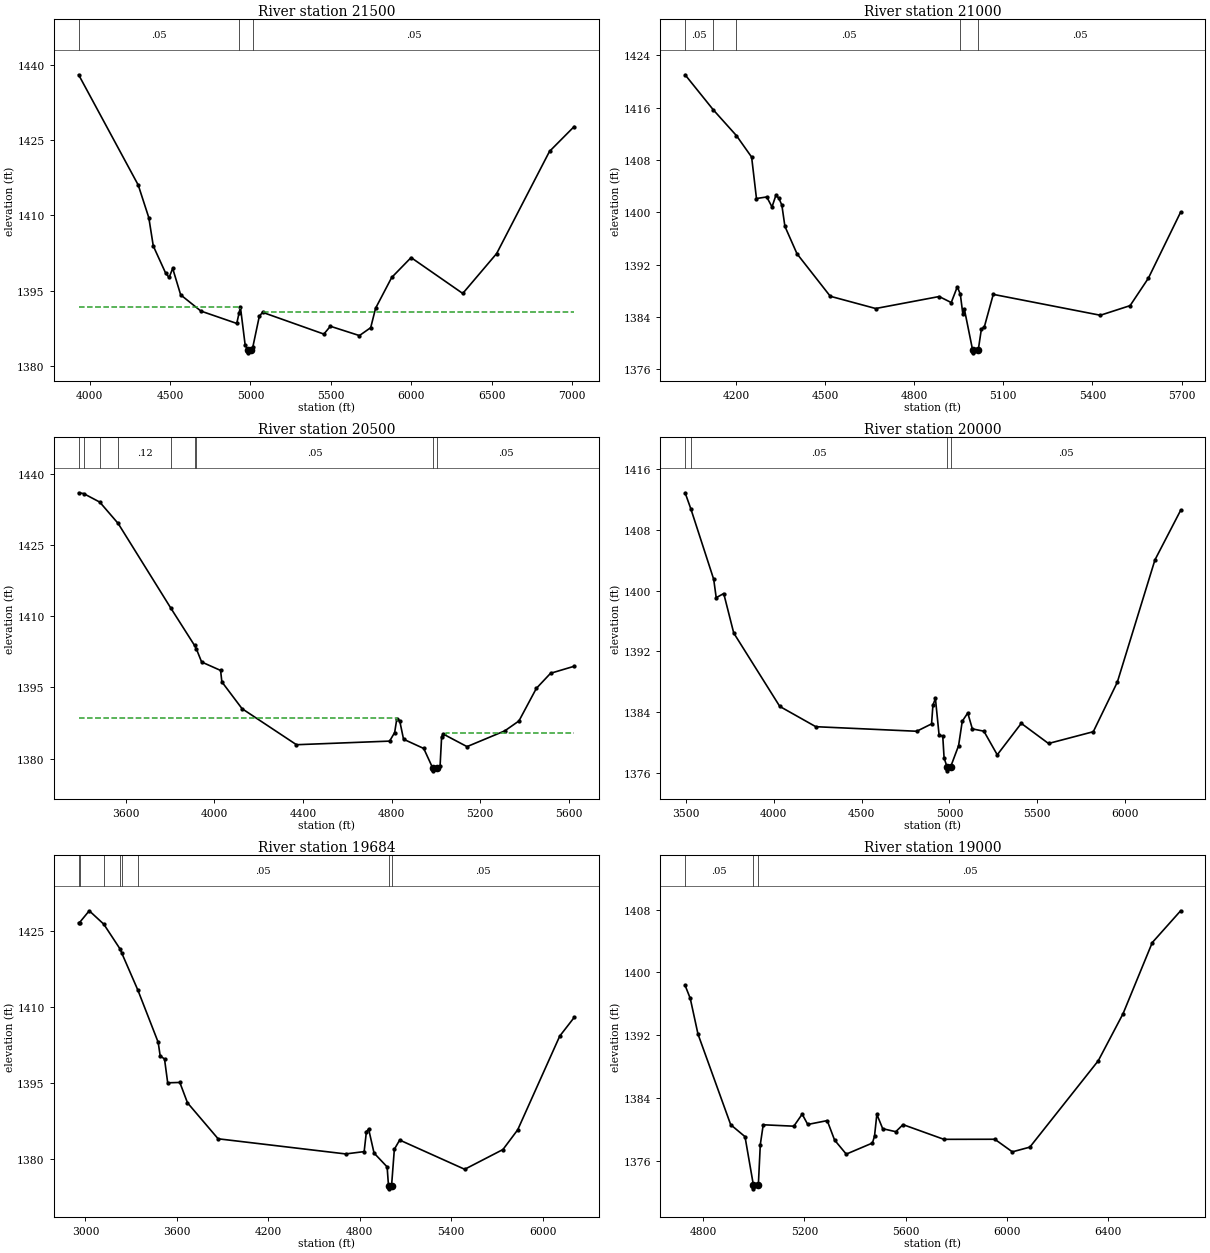
Type RM Length L Ch R = 1 ,21500   ,500,500,500
BEGIN DESCRIPTION:
FIELD CREEK 41.0
END DESCRIPTION:
XS GIS Cut Line= 3
      2732505.67      10294303.1      2731560.23     10293802.91
      2729555.66     10293603.11
#Sta/Elev= 30
  3930.4 1438.05  4301.3 1416.07  4367.3 1409.55    4395 1403.92  4471.7 1398.53
  4493.7 1397.64  4515.7 1399.46  4565.4 1394.18  4691.8 1390.94  4914.6 1388.48
  4928.2 1390.47  4937.3 1391.76  4966.5 1384.26  4984.4 1383.12  4984.9 1382.62
  5003.9 1383.12  5014.6 1383.78  5054.8 1389.89  5074.9  1390.7  5456.8 1386.36
    5497 1387.92  5677.9 1386.06  5748.2 1387.64  5778.4  1391.5  5878.9 1397.65
  5999.5 1401.61  6321.1 1394.46  6532.1 1402.42    6861 1422.78  7014.5 1427.73
#Mann= 3 ,-1 , 0
  3930.4     .05       0  4928.2     .05       0  5014.6     .05       0
#XS Ineff= 2 , 0
         4934.09 1391.85 5077.27          1390.8
Permanent Ineff=
       F       F
Bank Sta=4984.4,5003.9
XS Rating Curve= 0 ,0
Exp/Cntr=0.3,0.1

Type RM Length L Ch R = 1 ,21000   ,500,500,500
BEGIN DESCRIPTION:
FIELD CREEK 40.0
END DESCRIPTION:
XS GIS Cut Line= 3
      2732505.68     10293503.11      2731551.92     10293322.05
      2730855.71     10293353.11
#Sta/Elev= 30
  4029.2 1421.01  4124.4 1415.64  4202.1 1411.71  4253.1 1408.44  4269.4 1402.11
    4304 1402.35  4321.7 1400.82  4334.6 1402.58  4344.7 1402.18  4354.9 1401.08
  4365.1 1397.86  4405.8 1393.67  4517.8 1387.18  4670.5 1385.31  4884.2 1387.14
  4924.9 1386.22  4945.3 1388.63  4955.5 1387.48    4964 1384.43  4969.1 1385.21
  4996.5 1379.04    4997 1378.54    5016 1379.04  5026.3 1382.16  5036.3 1382.51
  5066.3 1387.47  5426.7 1384.28  5526.8 1385.75  5588.3 1389.94  5696.9 1400.03
#Mann= 5 ,-1 , 0
  4029.2     .05       0  4124.4     .12       0  4202.1     .05       0
  4955.5     .05       0    5016     .05       0
Bank Sta=4996.5,5016
XS Rating Curve= 0 ,0
Exp/Cntr=0.3,0.1

Type RM Length L Ch R = 1 ,20500   ,500,500,500
BEGIN DESCRIPTION:
FIELD CREEK 39.0
END DESCRIPTION:
XS GIS Cut Line= 3
      2732805.69     10293553.11      2731345.88     10292867.01
      2730855.68     10293253.11
#Sta/Elev= 30
    3387 1435.97  3409.2 1435.81  3482.3 1434.01  3565.4 1429.51  3803.2 1411.68
  3910.2 1403.83  3917.9 1403.17  3942.2 1400.34  4027.9 1398.56  4033.5 1396.16
  4124.7 1390.51  4370.4 1382.92  4790.8 1383.68  4813.6 1385.48  4823.4 1388.38
  4836.4 1387.96  4853.7 1384.08  4944.9 1382.13  4986.3 1377.92  4986.8 1377.42
  5005.8 1377.92  5018.6 1378.39  5025.7 1384.62  5033.1 1385.16  5140.3 1382.52
  5310.5 1385.83  5374.6 1387.92  5453.2 1394.78  5517.4 1397.96    5624 1399.44
#Mann= 9 ,-1 , 0
    3387     .05       0  3409.2     .12       0  3482.3     .05       0
  3565.4     .12       0  3803.2     .05       0  3910.2     .12       0
  3917.9     .05       0  4986.3     .05       0  5005.8     .05       0
#XS Ineff= 2 , 0
         4822.16 1388.64 5043.75          1385.4
Permanent Ineff=
       F       F
Bank Sta=4986.3,5005.8
XS Rating Curve= 0 ,0
Exp/Cntr=0.3,0.1

Type RM Length L Ch R = 1 ,20000   ,316,316,316
BEGIN DESCRIPTION:
FIELD CREEK 38.0
END DESCRIPTION:
XS GIS Cut Line= 3
       2732455.7     10293353.13      2731315.67     10292370.14
      2730055.69     10292753.11
#Sta/Elev= 30
  3494.7 1412.88  3527.2 1410.78  3657.6 1401.49  3671.9 1399.07  3714.7 1399.62
  3771.7 1394.42  4033.9 1384.76  4239.1 1382.09  4813.9 1381.49  4898.4 1382.46
  4906.1 1384.93  4920.3 1385.81  4941.2    1381  4962.1 1380.85  4969.7 1377.98
  4986.9 1376.78  4987.4 1376.28  5006.5 1376.78  5052.2 1379.59  5073.2 1382.81
  5104.5  1383.9  5130.6  1381.8  5196.3  1381.5  5272.5 1378.39  5409.3 1382.53
  5564.4 1379.88  5819.4 1381.43  5956.1 1387.94  6170.6 1404.05  6316.9 1410.57
#Mann= 4 ,-1 , 0
  3494.7     .12       0  3527.2     .05       0  4986.9     .03       0
  5006.5     .05       0
Bank Sta=4986.9,5006.5
XS Rating Curve= 0 ,0
Exp/Cntr=0.3,0.1

Type RM Length L Ch R = 1 ,19684   ,684,684,684
BEGIN DESCRIPTION:
FIELD CREEK 37.0
END DESCRIPTION:
XS GIS Cut Line= 3
      2732858.88     10293307.73      2731203.75       10292107.
      2730081.13     10292552.55
#Sta/Elev= 30
  2955.2 1426.61    2961 1426.63  3024.9 1428.96  3120.4 1426.31  3228.9 1421.34
  3239.3 1420.54  3344.3 1413.28  3477.2 1403.01  3490.4 1400.33  3518.9  1399.7
  3539.8    1395  3619.4 1395.07  3669.7 1391.05  3870.7 1383.95  4707.9 1380.96
  4829.3 1381.42    4844 1385.35  4858.7 1385.87  4894.3 1381.13  4980.1  1378.4
  4989.3 1374.57  4989.8 1374.07  5008.9 1374.57  5027.5 1381.89  5062.5  1383.7
  5489.2 1377.93  5740.3 1381.83  5837.1 1385.72    6113 1404.22  6207.8  1407.9
#Mann= 8 ,-1 , 0
  2955.2     .12       0    2961     .05       0  3120.4     .12       0
  3228.9     .05       0  3239.3     .12       0  3344.3     .05       0
  4989.3     .04       0  5008.9     .05       0
Bank Sta=4989.3,5008.9
XS Rating Curve= 0 ,0
Exp/Cntr=0.3,0.1

Type RM Length L Ch R = 1 ,19000   ,500,500,500
BEGIN DESCRIPTION:
FIELD CREEK 36.0
END DESCRIPTION:
XS GIS Cut Line= 3
      2731855.64     10291703.12      2731589.81     10291755.29
      2730055.66     10292453.12
#Sta/Elev= 30
  4729.1 1398.36  4749.4 1396.71    4780 1392.17  4909.1 1380.66  4965.6 1379.14
  4998.6 1373.01  4999.1 1372.51  5018.3 1373.01    5026 1378.13  5037.5 1380.65
  5158.3 1380.47  5191.3    1382  5213.3 1380.69  5290.2 1381.18  5319.2 1378.71
  5365.3 1376.92  5468.6 1378.33  5476.9 1379.21  5486.1 1381.98  5509.2 1380.15
  5560.8 1379.77  5589.4 1380.67  5750.8  1378.8  5951.8 1378.81    6021 1377.21
  6090.1 1377.81  6360.3 1388.79    6458 1394.76  6573.4  1403.8  6685.4 1407.84
#Mann= 3 ,-1 , 0
  4729.1     .05       0  4998.6     .03       0  5018.3     .05       0
Bank Sta=4998.6,5018.3
XS Rating Curve= 0 ,0
Exp/Cntr=0.3,0.1