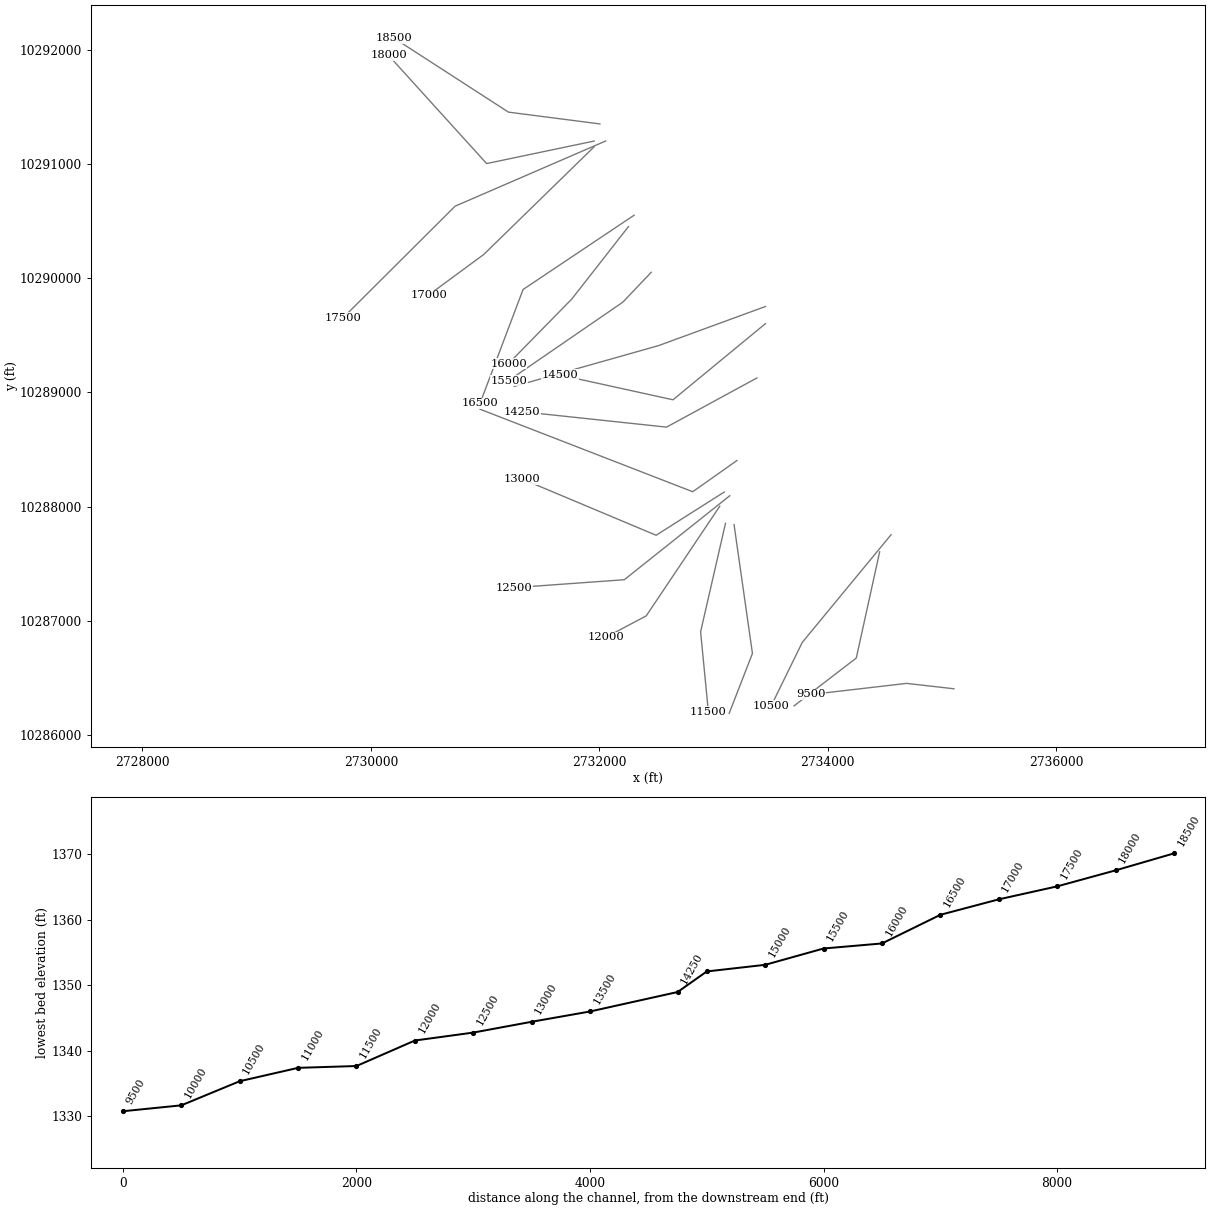
HEC-RAS study FIELD CREEK.prj: FIELD CREEK Base Level Engineering

--- FIELD CREEK.g01 (geometry) --- (continued)

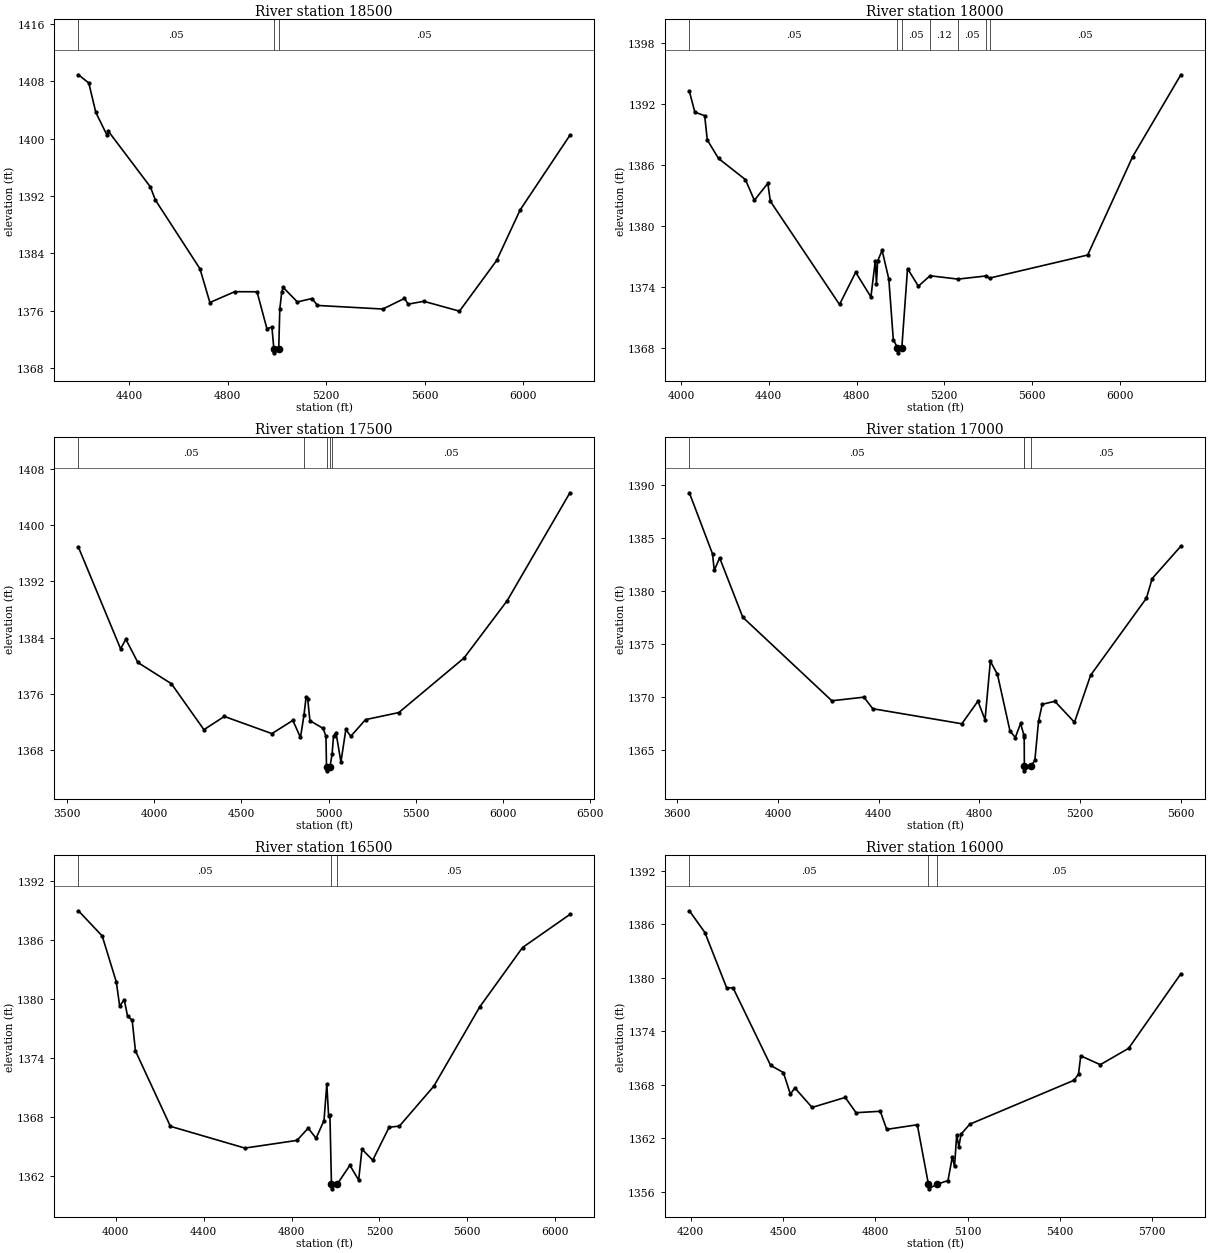
Type RM Length L Ch R = 1 ,18500   ,500,500,500
BEGIN DESCRIPTION:
FIELD CREEK 35.0
END DESCRIPTION:
XS GIS Cut Line= 3
      2732005.64     10291353.12      2731205.27     10291456.36
      2730205.66     10292103.13
#Sta/Elev= 30
    4193 1408.93  4235.2 1407.78  4263.5 1403.69  4309.6 1400.46  4314.6 1401.05
  4485.4 1393.27  4505.5 1391.45    4687 1381.83  4727.3 1377.12  4828.2 1378.63
  4918.9 1378.62  4959.2 1373.45  4979.4 1373.69  4987.4 1370.59  4987.9 1370.09
  5007.1 1370.59  5011.4 1376.16  5019.5 1378.65  5025.5 1379.22  5082.9  1377.2
  5142.4 1377.68  5164.6 1376.71  5430.4 1376.21  5518.1 1377.69  5533.3 1376.89
  5596.6 1377.29  5741.7 1375.91  5892.8 1382.99  5988.1 1390.04  6190.6 1400.48
#Mann= 3 ,-1 , 0
    4193     .05       0  4987.4     .04       0  5007.1     .05       0
Bank Sta=4987.4,5007.1
XS Rating Curve= 0 ,0
Exp/Cntr=0.3,0.1

Type RM Length L Ch R = 1 ,18000   ,500,500,500
BEGIN DESCRIPTION:
FIELD CREEK 34.0
END DESCRIPTION:
XS GIS Cut Line= 3
      2731955.73     10291203.12      2731014.01     10291005.64
      2730155.65     10291953.15
#Sta/Elev= 30
  4037.8 1393.26  4062.8  1391.2  4107.6 1390.85  4119.6 1388.46  4170.7 1386.64
  4293.3 1384.56  4334.2 1382.52  4395.5 1384.19    4407 1382.43  4722.4 1372.26
  4796.1 1375.43  4865.5    1373  4885.6 1376.59  4890.8 1374.26  4896.1 1376.54
  4916.6 1377.59  4947.2 1374.76  4967.6  1368.8  4986.7    1368  4987.2  1367.5
  5006.4    1368  5032.5  1375.8  5081.9 1374.06  5134.9 1375.09  5262.4 1374.76
  5389.9 1375.07  5406.3 1374.86  5853.7 1377.13  6059.1 1386.83  6278.5 1394.88
#Mann= 7 ,-1 , 0
  4037.8     .05       0  4986.7     .05       0  5006.4     .05       0
  5134.9     .12       0  5262.4     .05       0  5389.9     .12       0
  5406.3     .05       0
Bank Sta=4986.7,5006.4
XS Rating Curve= 0 ,0
Exp/Cntr=0.3,0.1

Type RM Length L Ch R = 1 ,17500   ,500,500,500
BEGIN DESCRIPTION:
FIELD CREEK 33.0
END DESCRIPTION:
XS GIS Cut Line= 3
      2732055.66      10291203.1      2730737.65     10290632.05
      2729755.66     10289653.09
#Sta/Elev= 30
  3563.6 1396.85  3805.7 1382.41    3836 1383.76    3905 1380.46  4097.6 1377.44
  4284.4 1370.91  4401.7 1372.79  4675.2 1370.35  4795.1 1372.23    4839  1369.8
    4859 1372.96  4871.4 1375.57  4880.5 1375.27  4893.2 1372.19  4969.4 1371.09
  4985.3 1369.96  4988.5 1365.56    4989 1365.06  5008.2 1365.56  5020.8 1367.49
  5028.9 1370.04  5043.1 1370.49  5071.4 1366.31  5099.6 1370.94  5127.9 1369.97
  5212.8 1372.34  5403.7 1373.34  5778.5  1381.1  6025.9 1389.23  6386.6 1404.58
#Mann= 5 ,-1 , 0
  3563.6     .05       0    4859     .12       0  4988.5     .07       0
  5008.2     .12       0  5020.8     .05       0
Bank Sta=4988.5,5008.2
XS Rating Curve= 0 ,0
Exp/Cntr=0.3,0.1

Type RM Length L Ch R = 1 ,17000   ,500,500,500
BEGIN DESCRIPTION:
FIELD CREEK 32.0
END DESCRIPTION:
XS GIS Cut Line= 3
      2731955.68     10291153.11      2730988.44     10290208.76
       2730505.7     10289853.12
#Sta/Elev= 30
  3648.2 1389.31  3740.1 1383.55  3747.1 1381.99  3768.4 1383.17  3860.3 1377.57
  4213.9 1369.69  4341.2 1370.03  4376.5 1368.94  4730.1 1367.52  4793.9 1369.65
  4822.2  1367.9  4843.3 1373.42  4871.6 1372.17    4921 1366.86  4942.3 1366.22
  4963.4 1367.55  4976.6 1366.44  4977.6 1366.28  4978.3 1363.58  4978.8 1363.08
  5005.2 1363.58    5020 1364.07  5034.6 1367.77  5049.3 1369.36  5099.4 1369.64
  5177.3 1367.66  5241.4  1372.1    5463 1379.37  5485.8 1381.22  5599.6 1384.27
#Mann= 4 ,-1 , 0
  3648.2     .05       0  4976.6     .12       0  4978.3     .07       0
  5005.2     .05       0
Bank Sta=4978.3,5005.2
XS Rating Curve= 0 ,0
Exp/Cntr=0.3,0.1

Type RM Length L Ch R = 1 ,16500   ,500,500,500
BEGIN DESCRIPTION:
FIELD CREEK 31.0
END DESCRIPTION:
XS GIS Cut Line= 3
      2732305.71     10290553.13      2731333.11     10289902.06
      2730955.67     10288903.08
#Sta/Elev= 30
  3829.6 1388.96  3937.9  1386.4  4002.3 1381.72  4017.3 1379.29  4038.3 1379.92
  4053.3 1378.27  4074.3 1377.84  4089.3 1374.73  4248.4 1367.07  4587.7 1364.86
  4824.9 1365.64  4875.9 1366.88  4911.9 1365.86    4948 1367.66  4960.8 1371.36
    4969 1368.12    4975 1368.17  4981.9 1361.22  4982.4 1360.72  5008.9 1361.22
  5065.9 1363.11  5105.8 1361.61  5120.9 1364.75  5169.9 1363.63  5244.7 1366.98
  5291.3 1367.09  5447.9 1371.14    5657 1379.19  5852.2 1385.23  6067.9 1388.59
#Mann= 3 ,-1 , 0
  3829.6     .05       0  4981.9     .03       0  5008.9     .05       0
Bank Sta=4981.9,5008.9
XS Rating Curve= 0 ,0
Exp/Cntr=0.3,0.1

Type RM Length L Ch R = 1 ,16000   ,500,500,500
BEGIN DESCRIPTION:
FIELD CREEK 30.0
END DESCRIPTION:
XS GIS Cut Line= 3
      2732255.67     10290453.09      2731760.61     10289819.58
      2731205.68      10289253.1
#Sta/Elev= 30
    4196  1387.5  4246.6 1385.06  4317.2 1378.87    4338 1378.87    4460 1370.18
  4501.7 1369.37  4524.3 1366.95  4538.6 1367.66  4594.8 1365.47  4702.4 1366.59
  4737.7 1364.88  4816.4 1365.04  4837.2 1363.01  4936.7 1363.53  4972.9 1356.85
  4973.4 1356.35    5000 1356.85  5036.4 1357.28  5050.6 1359.95  5057.6 1358.86
  5064.7  1362.4  5071.7 1361.05  5078.8 1362.47  5107.1 1363.59  5446.5 1368.52
  5460.6 1369.22  5467.7 1371.25  5531.3 1370.26  5623.3 1372.09    5793 1380.44
#Mann= 3 ,-1 , 0
    4196     .05       0  4972.9     .03       0    5000     .05       0
Bank Sta=4972.9,5000
XS Rating Curve= 0 ,0
Exp/Cntr=0.3,0.1

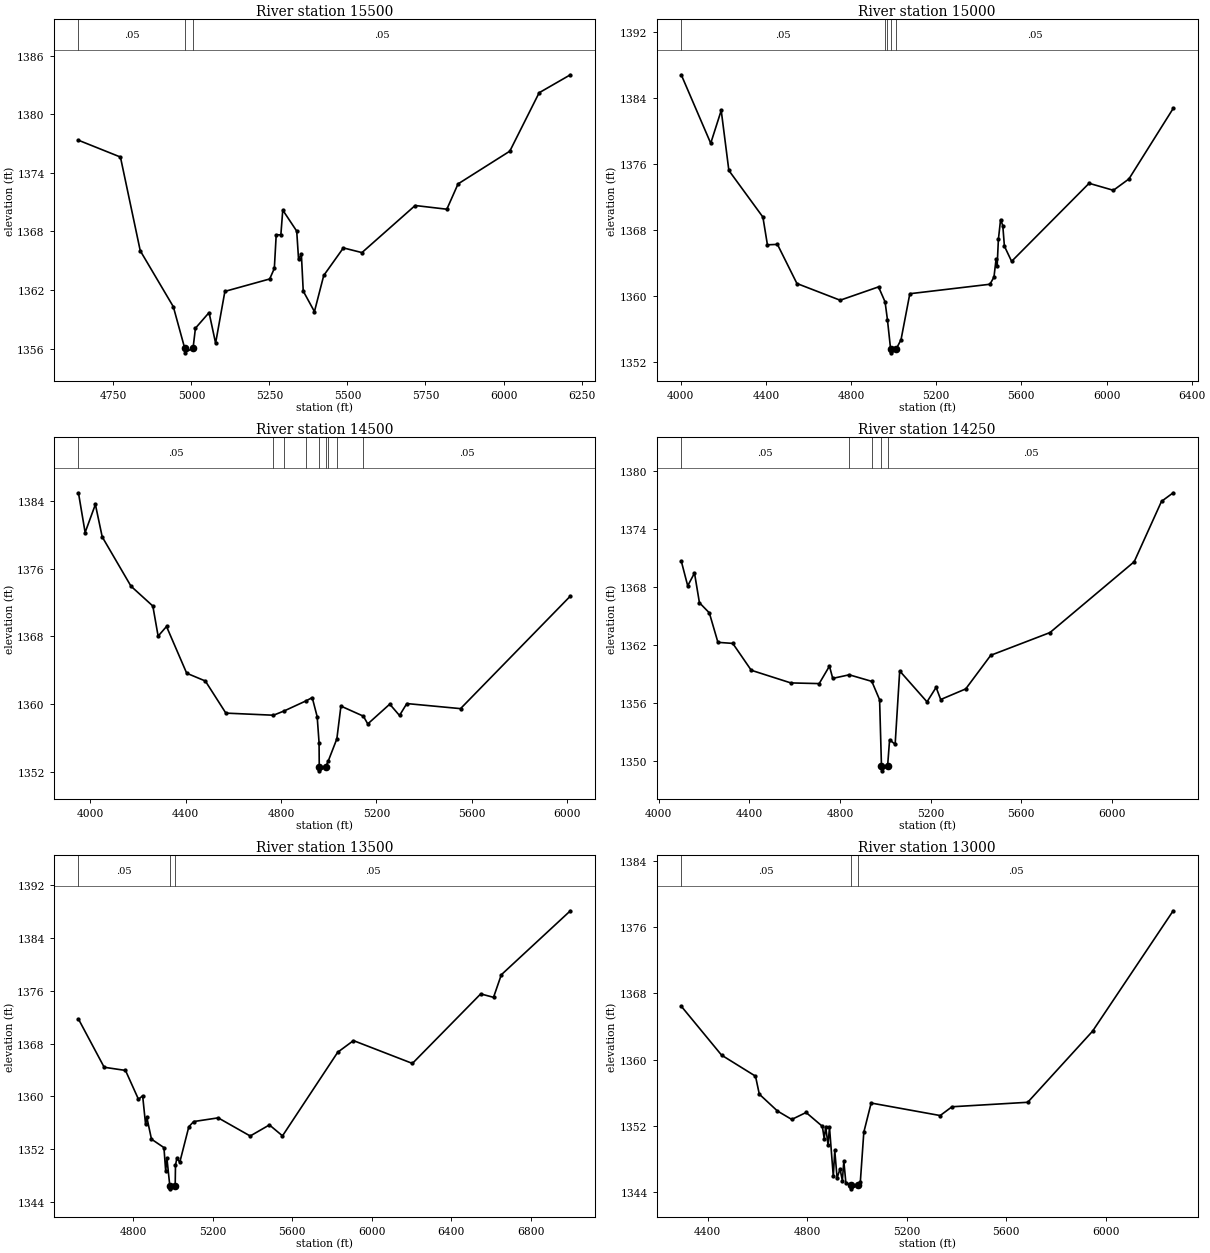
Type RM Length L Ch R = 1 ,15500   ,500,500,500
BEGIN DESCRIPTION:
FIELD CREEK 29.0
END DESCRIPTION:
XS GIS Cut Line= 3
      2732455.69     10290053.12      2732206.35     10289790.83
      2731205.68     10289103.11
#Sta/Elev= 30
  4638.1 1377.34  4772.6 1375.62  4836.1 1366.03  4942.1  1360.3  4978.3 1356.08
  4978.8 1355.58  5005.4 1356.08  5012.9  1358.1  5056.6  1359.7  5077.5 1356.57
  5107.3 1361.87  5250.8 1363.14  5265.7 1364.22  5271.7 1367.66  5286.6 1367.66
  5292.7 1370.19  5337.4 1368.04  5343.4 1365.14  5352.3 1365.68  5358.3  1361.9
  5394.2  1359.8    5424  1363.5  5486.9 1366.32  5546.4 1365.84  5716.9 1370.66
  5818.4 1370.28  5854.3 1372.87  6020.1 1376.22  6114.1  1382.2  6214.2 1384.04
#Mann= 3 ,-1 , 0
  4638.1     .05       0  4978.3     .03       0  5005.4     .05       0
Bank Sta=4978.3,5005.4
XS Rating Curve= 0 ,0
Exp/Cntr=0.3,0.1

Type RM Length L Ch R = 1 ,15000   ,500,500,500
BEGIN DESCRIPTION:
FIELD CREEK 28.0
END DESCRIPTION:
XS GIS Cut Line= 3
      2733455.69     10289753.11      2732519.19     10289410.21
      2731255.69     10289053.11
#Sta/Elev= 30
  4002.7 1386.86  4141.1 1378.54  4190.4 1382.53  4226.3 1375.24  4386.1 1369.58
  4407.4 1366.21  4454.4 1366.26  4545.9 1361.51  4748.9 1359.48  4929.2  1361.1
  4959.9 1359.28    4971 1357.12  4985.7 1353.59  4986.2 1353.09  5012.8 1353.59
  5034.8 1354.68  5076.2 1360.27  5452.3 1361.42  5471.3 1362.28  5481.1 1364.44
  5486.3 1363.64  5492.1 1366.86  5502.4 1369.27  5512.8 1368.54  5520.3 1366.05
  5554.2  1364.2  5918.1 1373.68  6032.2 1372.83  6105.2 1374.21    6313 1382.77
#Mann= 5 ,-1 , 0
  4002.7     .05       0  4959.9     .12       0    4971     .05       0
  4985.7     .04       0  5012.8     .05       0
Bank Sta=4985.7,5012.8
XS Rating Curve= 0 ,0
Exp/Cntr=0.3,0.1

Type RM Length L Ch R = 1 ,14500   ,250,250,250
BEGIN DESCRIPTION:
FIELD CREEK 27.0
END DESCRIPTION:
XS GIS Cut Line= 3
      2733455.67      10289603.1      2732645.89      10288935.5
      2731655.72      10289153.1
#Sta/Elev= 30
  3950.5 1384.98  3978.5 1380.28  4021.5  1383.6  4050.2 1379.76  4170.8 1373.93
  4262.5 1371.58  4284.7 1368.02  4319.9 1369.16  4404.5 1363.63  4482.7 1362.71
  4568.8 1358.91  4768.5 1358.66  4814.3 1359.18  4905.1 1360.36    4931 1360.75
  4951.8 1358.49  4959.7 1355.42  4960.5 1352.58    4961 1352.08  4987.6 1352.58
  4997.8 1353.21  5034.3 1355.86  5051.4 1359.74  5145.5 1358.55    5164 1357.63
  5256.2 1359.97  5297.1 1358.63  5327.8 1360.04  5553.1 1359.44  6013.8 1372.76
#Mann= 9 ,-1 , 0
  3950.5     .05       0  4768.5     .12       0  4814.3     .05       0
  4905.1     .12       0  4960.5     .04       0  4987.6     .12       0
  4997.8     .05       0  5034.3     .12       0  5145.5     .05       0
Bank Sta=4960.5,4987.6
XS Rating Curve= 0 ,0
Exp/Cntr=0.3,0.1

Type RM Length L Ch R = 1 ,14250   ,750,750,750
BEGIN DESCRIPTION:
FIELD CREEK 26.0
END DESCRIPTION:
XS GIS Cut Line= 3
      2733380.68     10289126.83      2732589.25       10288696.
      2731324.34     10288831.06
#Sta/Elev= 30
  4098.9 1370.66  4127.4 1368.09  4157.4 1369.41  4179.2 1366.34  4222.9 1365.29
  4260.9 1362.24  4326.5 1362.13  4408.1 1359.35  4582.9 1358.04  4708.2 1357.97
  4753.6 1359.78  4768.1 1358.51    4841 1358.88  4940.7  1358.2  4975.1  1356.3
  4983.4 1349.44  4983.9 1348.94  5010.5 1349.44  5019.3 1352.16  5043.8 1351.68
  5063.9 1359.28  5184.6 1356.08  5224.8 1357.58    5245 1356.32  5355.6 1357.42
  5466.2  1360.9  5727.7 1363.25  6099.8 1370.58  6220.5 1376.83  6272.1 1377.72
#Mann= 5 ,-1 , 0
  4098.9     .05       0    4841     .12       0  4940.7     .05       0
  4983.4     .03       0  5010.5     .05       0
Bank Sta=4983.4,5010.5
XS Rating Curve= 0 ,0
Exp/Cntr=0.3,0.1

Type RM Length L Ch R = 1 ,13500   ,500,500,500
BEGIN DESCRIPTION:
FIELD CREEK 25.0
END DESCRIPTION:
XS GIS Cut Line= 3
      2733205.72     10288403.14      2732818.67     10288129.87
      2730955.64     10288853.13
#Sta/Elev= 30
  4526.2 1371.71  4655.5  1364.4  4762.6 1363.92  4827.9 1359.54  4848.8 1360.08
  4863.6 1355.74  4869.7 1356.83  4893.2  1353.5  4955.9 1352.22  4964.6 1348.67
  4970.7 1350.63  4985.2 1346.47  4985.7 1345.97  5012.4 1346.47  5013.9 1349.55
    5021 1350.63  5035.4 1349.99  5080.9 1355.38  5105.4 1356.17  5228.5 1356.73
  5389.4 1353.98  5485.9 1355.66  5551.7    1354  5829.3 1366.68  5908.3 1368.44
  6204.6 1364.98  6547.9 1375.52  6612.3    1375  6651.4 1378.42  6998.5 1388.12
#Mann= 3 ,-1 , 0
  4526.2     .05       0  4985.2     .04       0  5012.4     .05       0
Bank Sta=4985.2,5012.4
XS Rating Curve= 0 ,0
Exp/Cntr=0.3,0.1

Type RM Length L Ch R = 1 ,13000   ,500,500,500
BEGIN DESCRIPTION:
FIELD CREEK 24.0
END DESCRIPTION:
XS GIS Cut Line= 3
       2733094.2     10288126.95      2732498.14     10287748.42
       2731326.9     10288240.48
#Sta/Elev= 30
  4293.9 1366.43  4455.8 1360.53  4592.2 1357.99  4607.5 1355.82  4680.3 1353.79
  4737.9 1352.77  4795.5 1353.61  4860.8 1351.94  4868.3 1350.45  4874.3 1351.91
  4883.6  1349.7  4889.5 1351.82  4904.8  1345.9  4910.7 1349.03    4920  1345.7
  4931.9 1346.81  4941.2 1345.39  4947.1 1347.74  4955.5 1345.07  4977.4  1344.9
  4977.9  1344.4  5004.7  1344.9  5013.5 1345.27  5027.4 1351.23  5056.9 1354.75
  5334.2 1353.24  5381.7  1354.3    5686 1354.84  5946.3 1363.41  6270.4 1377.94
#Mann= 3 ,-1 , 0
  4293.9     .05       0  4977.4     .04       0  5004.7     .05       0
Bank Sta=4977.4,5004.7
XS Rating Curve= 0 ,0
Exp/Cntr=0.3,0.1

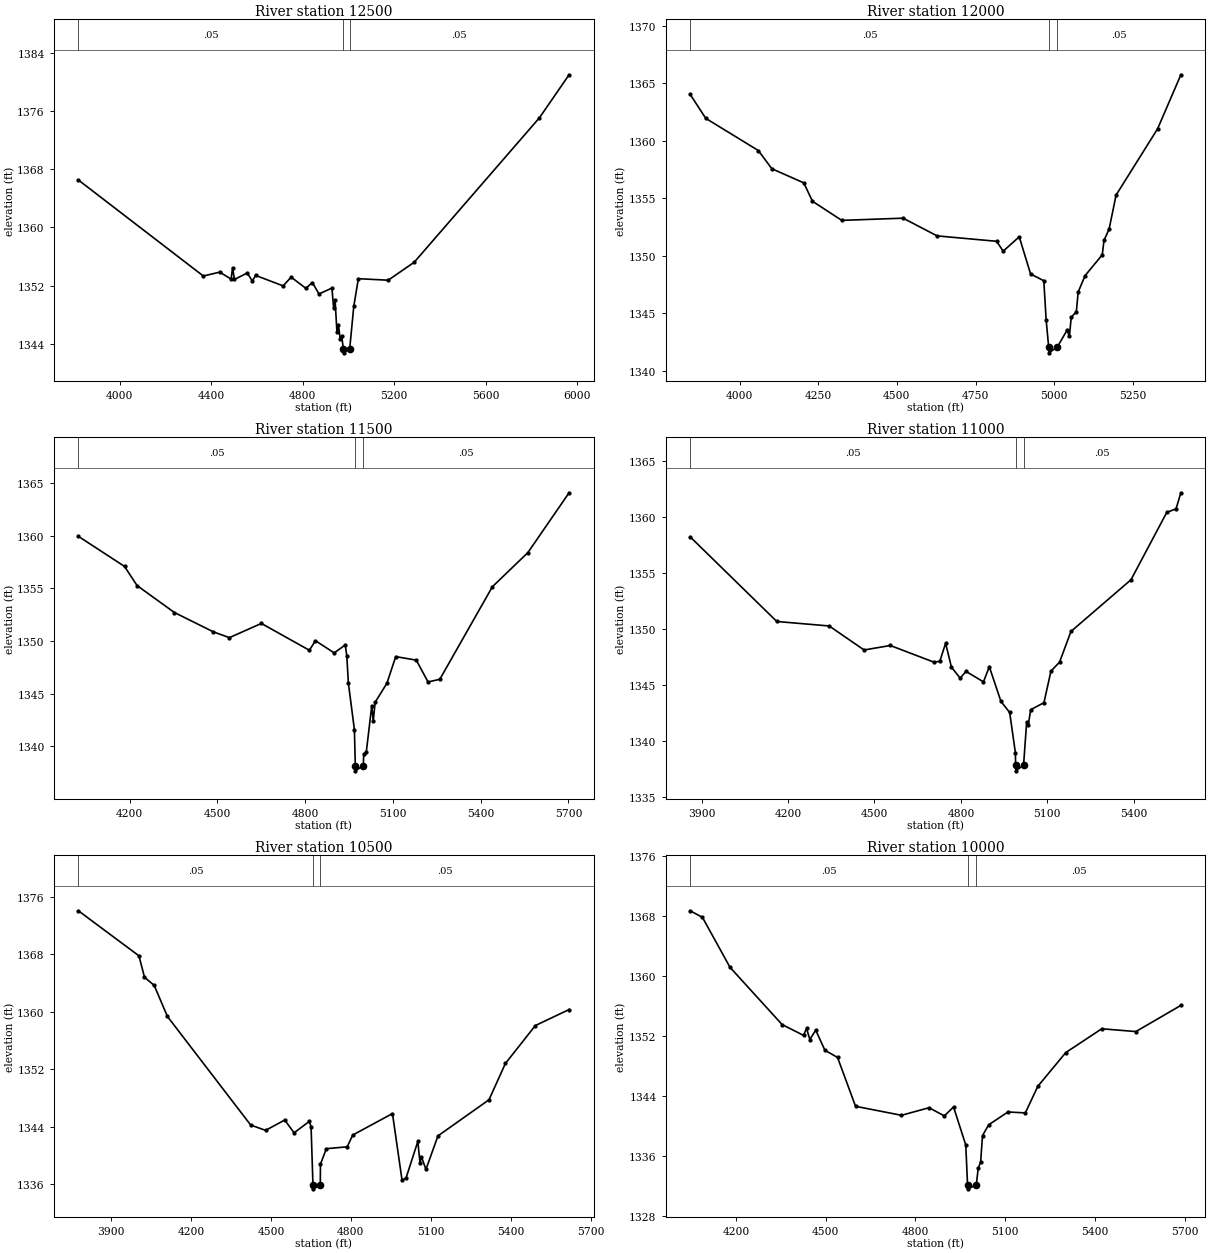
Type RM Length L Ch R = 1 ,12500   ,500,500,500
BEGIN DESCRIPTION:
FIELD CREEK 23.0
END DESCRIPTION:
XS GIS Cut Line= 3
      2733142.88     10288094.55      2732219.62     10287358.75
      2731256.62     10287289.25
#Sta/Elev= 30
  3819.4  1366.5  4365.7 1353.31  4437.7 1353.84  4487.4 1352.88  4493.8 1354.45
  4501.8 1352.83  4557.8 1353.72  4580.3 1352.62  4594.7 1353.39  4714.8 1351.95
    4750 1353.15    4814 1351.62  4842.9 1352.41  4871.7 1350.84  4928.3 1351.65
  4935.8 1348.89  4942.2 1349.97  4950.2  1345.6  4956.6 1346.64  4964.6  1344.6
    4971 1345.03  4978.6 1343.25  4979.1 1342.75  5005.9 1343.25    5024 1349.18
    5044 1352.94  5174.4 1352.73  5288.2  1355.2  5836.1 1375.06  5965.5 1380.96
#Mann= 3 ,-1 , 0
  3819.4     .05       0  4978.6     .04       0  5005.9     .05       0
Bank Sta=4978.6,5005.9
XS Rating Curve= 0 ,0
Exp/Cntr=0.3,0.1

Type RM Length L Ch R = 1 ,12000   ,500,500,500
BEGIN DESCRIPTION:
FIELD CREEK 22.0
END DESCRIPTION:
XS GIS Cut Line= 3
      2733055.69     10288003.11      2732411.55       10287042.
      2732055.68     10286853.11
#Sta/Elev= 30
    3843 1364.01  3892.5 1361.93  4059.7 1359.13  4102.6 1357.55  4204.1 1356.32
  4231.7 1354.72  4324.8 1353.06  4519.9 1353.25  4627.9 1351.71    4817 1351.24
    4838 1350.38    4889 1351.63  4925.1  1348.4  4967.1 1347.81  4974.6  1344.4
  4982.6 1342.04  4983.1 1341.54    5010 1342.04  5040.6 1343.49  5048.6    1343
  5054.3 1344.63  5070.6 1345.12  5076.3 1346.82  5098.2 1348.25  5152.9 1350.06
  5158.5 1351.31  5174.9 1352.32  5196.9 1355.26  5328.8 1361.02  5402.9 1365.72
#Mann= 3 ,-1 , 0
    3843     .05       0  4982.6     .04       0    5010     .05       0
Bank Sta=4982.6,5010
XS Rating Curve= 0 ,0
Exp/Cntr=0.3,0.1

Type RM Length L Ch R = 1 ,11500   ,500,500,500
BEGIN DESCRIPTION:
FIELD CREEK 21.0
END DESCRIPTION:
XS GIS Cut Line= 3
      2733105.68     10287853.11      2732887.67     10286902.08
      2732955.69     10286203.08
#Sta/Elev= 30
  4024.3 1359.94  4182.1 1357.08    4225 1355.26  4352.6  1352.7    4486 1350.86
  4540.7 1350.31  4650.1 1351.66  4814.3 1349.11  4834.8 1350.02  4899.2 1348.86
    4937 1349.62  4942.1  1348.6  4947.6 1345.99  4968.2 1341.56  4971.3 1338.15
  4971.8 1337.65  4998.7 1338.15    5000 1339.22    5009 1339.47  5027.6 1343.85
  5032.6 1342.35  5039.1 1344.17  5079.3 1345.97  5109.5 1348.51  5179.8 1348.17
    5220  1346.1  5260.2 1346.35  5440.1 1355.15  5561.6  1358.4  5702.3 1364.08
#Mann= 3 ,-1 , 0
  4024.3     .05       0  4971.3     .05       0  4998.7     .05       0
Bank Sta=4971.3,4998.7
XS Rating Curve= 0 ,0
Exp/Cntr=0.3,0.1

Type RM Length L Ch R = 1 ,11000   ,500,500,500
BEGIN DESCRIPTION:
FIELD CREEK 20.0
END DESCRIPTION:
XS GIS Cut Line= 3
       2733180.7     10287840.57      2733341.57     10286712.59
      2733137.75     10286187.45
#Sta/Elev= 30
  3860.6 1358.22  4161.1 1350.68  4342.9 1350.28  4464.1 1348.14    4555 1348.54
  4705.9 1347.06  4726.7 1347.13  4746.9 1348.74  4767.1 1346.61  4797.4 1345.63
  4817.6 1346.23  4878.3  1345.3  4898.5 1346.65  4938.9 1343.56  4969.2 1342.57
    4989 1338.99  4989.9 1337.87  4990.4 1337.37  5017.4 1337.87  5028.2 1341.74
  5033.5 1341.45  5042.3 1342.82    5088 1343.44  5112.5 1346.26  5142.4 1347.06
  5181.8 1349.79  5390.2  1354.4  5514.3  1360.4  5546.5 1360.72  5563.3 1362.15
#Mann= 3 ,-1 , 0
  3860.6     .05       0  4989.9     .05       0  5017.4     .05       0
Bank Sta=4989.9,5017.4
XS Rating Curve= 0 ,0
Exp/Cntr=0.3,0.1

Type RM Length L Ch R = 1 ,10500   ,500,500,500
BEGIN DESCRIPTION:
FIELD CREEK 19.0
END DESCRIPTION:
XS GIS Cut Line= 3
      2734555.66     10287753.08      2733777.91      10286809.5
      2733505.69     10286253.13
#Sta/Elev= 30
  3777.2 1374.04  4004.5 1367.77  4025.4 1364.79  4061.9 1363.65  4111.4 1359.33
  4424.1 1344.21  4480.1 1343.47  4551.8 1344.91    4587 1343.13  4644.3 1344.72
  4650.8 1343.96  4657.9 1335.83  4658.4 1335.33  4685.4 1335.83    4686 1338.76
  4708.2 1340.92  4786.4 1341.18  4807.2 1342.82  4956.4 1345.81  4992.2 1336.56
  5007.1 1336.81  5051.6 1341.93  5059.6 1338.97  5065.1 1339.78  5082.1 1338.04
  5127.1  1342.7  5318.8 1347.73  5380.3 1352.78  5492.8 1358.06  5619.4 1360.29
#Mann= 3 ,-1 , 0
  3777.2     .05       0  4657.9     .03       0  4685.4     .05       0
Bank Sta=4657.9,4685.4
XS Rating Curve= 0 ,0
Exp/Cntr=0.3,0.1

Type RM Length L Ch R = 1 ,10000   ,500,500,500
BEGIN DESCRIPTION:
FIELD CREEK 18.0
END DESCRIPTION:
XS GIS Cut Line= 3
      2734455.69     10287603.13      2734250.93     10286672.39
       2733705.7     10286253.12
#Sta/Elev= 30
    4047 1368.74    4088 1367.86  4180.1  1361.2  4354.4 1353.56  4425.9 1352.12
  4436.1 1353.06  4447.1 1351.57  4466.8 1352.82  4497.5 1350.13  4539.7 1349.18
  4599.9 1342.66  4753.5 1341.46  4845.7 1342.47  4896.9 1341.38  4927.6 1342.57
  4968.5 1337.49  4974.5 1332.15    4975 1331.65  5003.6 1332.15    5010 1334.37
  5018.2 1335.25  5024.5 1338.76  5045.3  1340.2  5109.6  1341.9  5167.7 1341.78
  5209.3 1345.32  5302.7 1349.82  5423.2    1353  5537.4 1352.63  5687.8 1356.12
#Mann= 3 ,-1 , 0
    4047     .05       0  4974.5     .05       0  5003.6     .05       0
Bank Sta=4974.5,5003.6
XS Rating Curve= 0 ,0
Exp/Cntr=0.3,0.1

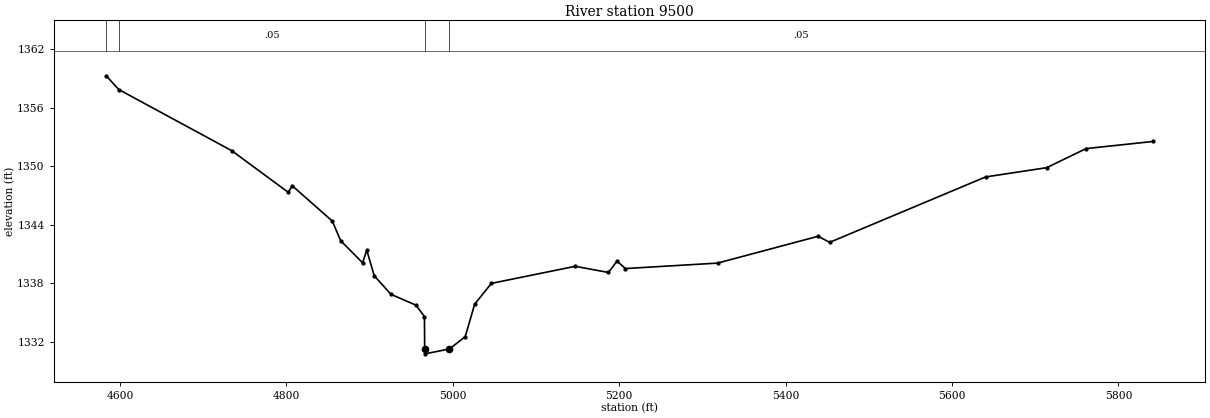
Type RM Length L Ch R = 1 ,9500    ,500,500,500
BEGIN DESCRIPTION:
FIELD CREEK 17.0
END DESCRIPTION:
XS GIS Cut Line= 3
      2735105.71     10286403.11      2734691.68     10286450.26
      2733855.71     10286353.11
#Sta/Elev= 30
  4583.3 1359.28  4598.4 1357.87  4734.3 1351.59    4802 1347.33    4807 1347.99
  4855.1 1344.37  4865.1 1342.36  4891.5 1340.09  4896.5 1341.39  4905.4 1338.77
  4925.5 1336.86  4955.7 1335.74  4965.8 1334.58  4966.1 1331.25  4966.6 1330.75
  4995.9 1331.25  5014.8 1332.51  5026.2 1335.85  5046.3 1337.98    5147 1339.73
    5187  1339.1  5197.3 1340.27  5207.4  1339.5  5318.1 1340.06  5438.9 1342.81
  5452.9 1342.19  5640.3  1348.9  5713.7 1349.85  5761.1 1351.81  5841.6 1352.54
#Mann= 4 ,-1 , 0
  4583.3     .12       0  4598.4     .05       0  4966.1     .05       0
  4995.9     .05       0
Bank Sta=4966.1,4995.9
XS Rating Curve= 0 ,0
Exp/Cntr=0.3,0.1