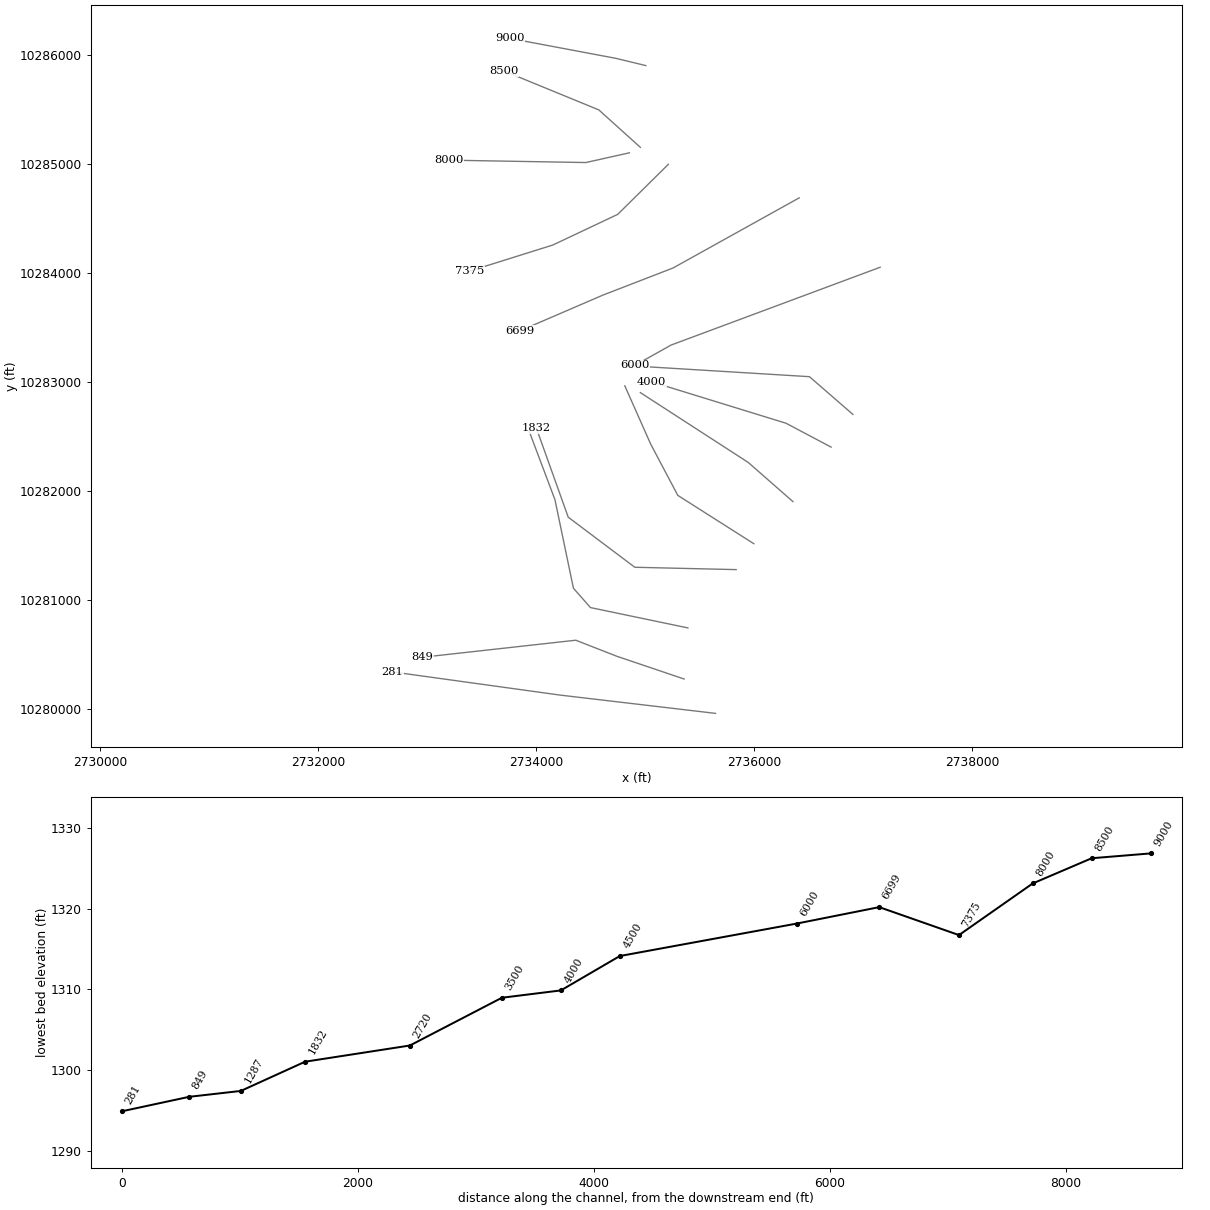
HEC-RAS study FIELD CREEK.prj: FIELD CREEK Base Level Engineering

--- FIELD CREEK.g01 (geometry) --- (continued)

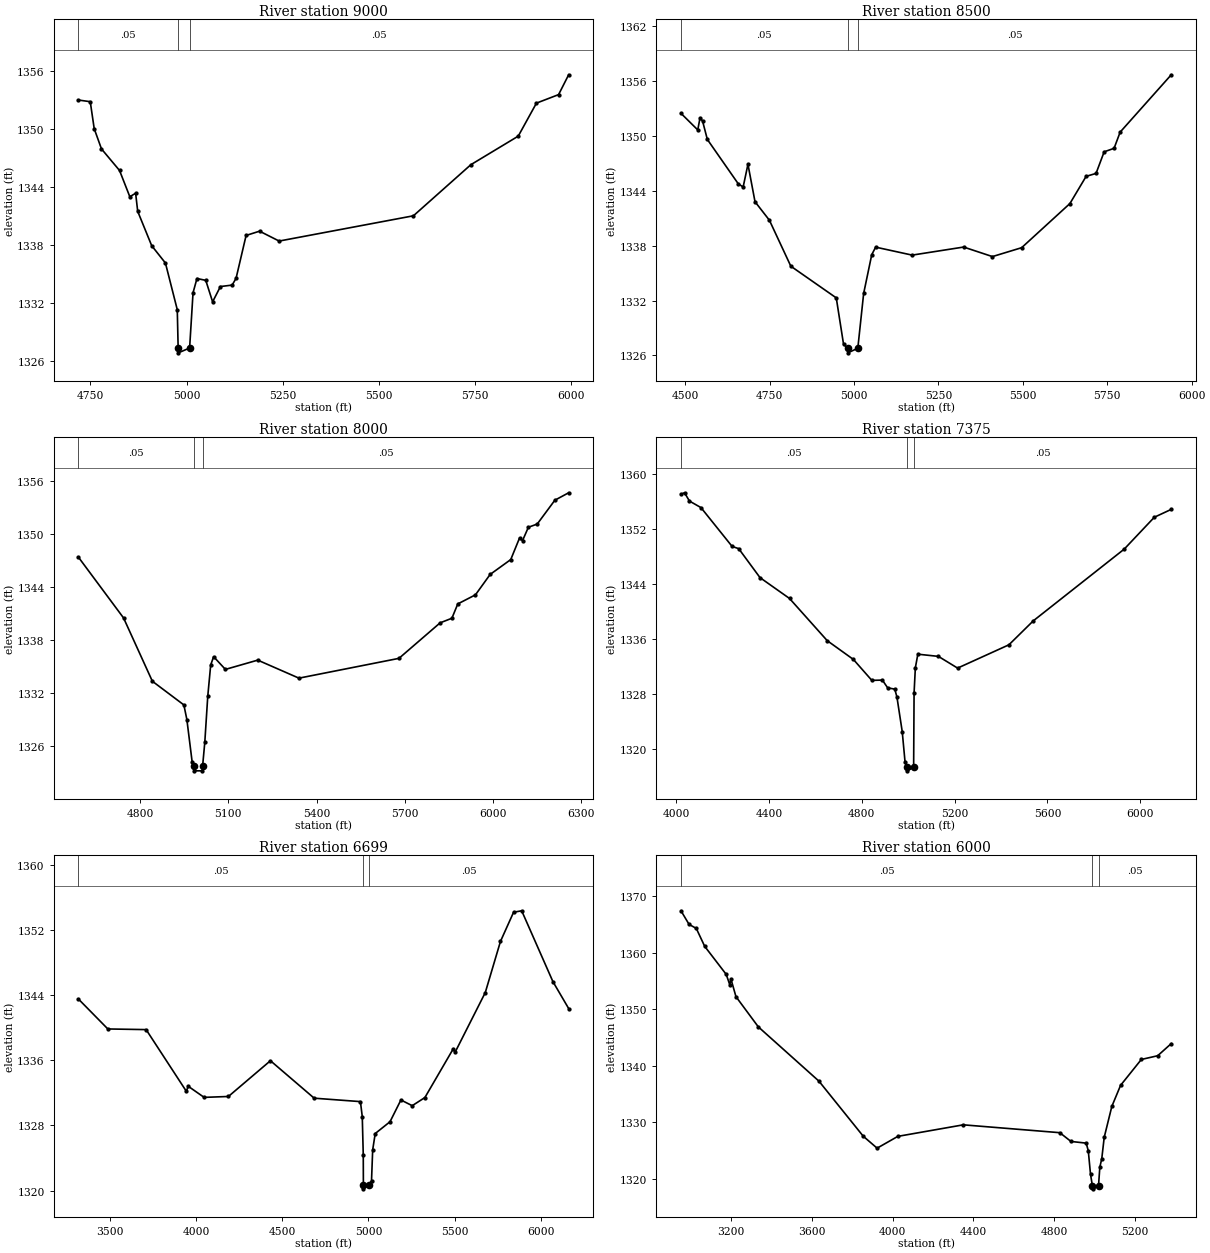
Type RM Length L Ch R = 1 ,9000    ,500,500,500
BEGIN DESCRIPTION:
FIELD CREEK 16.0
END DESCRIPTION:
XS GIS Cut Line= 3
      2735005.68     10285903.11      2734732.28     10285969.33
      2733755.73      10286153.1
#Sta/Elev= 30
  4718.7 1353.01  4749.6 1352.84  4759.9 1350.05  4778.8 1347.96  4825.8 1345.73
  4852.5 1343.02  4867.6 1343.38    4873 1341.51  4909.4 1337.96  4945.1 1336.17
  4975.9 1331.35  4978.2 1327.39  4978.7 1326.89    5008 1327.39  5016.9  1333.1
  5027.1 1334.57    5050 1334.38  5067.8 1332.16  5088.1 1333.74  5118.6 1333.89
  5128.8 1334.59  5154.9 1339.02  5189.9 1339.46  5240.8 1338.44    5590 1341.05
  5739.4 1346.33  5862.6 1349.28  5909.9 1352.69  5967.5 1353.57  5993.7 1355.62
#Mann= 3 ,-1 , 0
  4718.7     .05       0  4978.2     .05       0    5008     .05       0
Bank Sta=4978.2,5008
XS Rating Curve= 0 ,0
Exp/Cntr=0.3,0.1

Type RM Length L Ch R = 1 ,8500    ,500,500,500
BEGIN DESCRIPTION:
FIELD CREEK 15.0
END DESCRIPTION:
XS GIS Cut Line= 3
      2734955.66     10285153.13      2734574.93     10285496.51
      2733705.64     10285853.13
#Sta/Elev= 30
  4487.3 1352.44    4537 1350.63  4543.7 1351.94  4551.2 1351.61  4565.4 1349.59
  4657.3 1344.73  4671.5  1344.4  4685.7 1346.88  4706.6 1342.79  4749.2 1340.77
  4812.7 1335.75  4947.3 1332.29  4968.9 1327.22  4981.2 1326.79  4981.7 1326.29
  5011.1 1326.79  5028.4 1332.77  5052.4 1337.01    5064 1337.83  5172.1 1336.96
  5324.6 1337.84  5409.9  1336.8  5496.4 1337.77  5639.4 1342.59  5687.4 1345.56
  5716.8 1345.88  5740.8 1348.24  5770.2 1348.62  5788.2 1350.39  5939.6 1356.65
#Mann= 3 ,-1 , 0
  4487.3     .05       0  4981.2     .03       0  5011.1     .05       0
Bank Sta=4981.2,5011.1
XS Rating Curve= 0 ,0
Exp/Cntr=0.3,0.1

Type RM Length L Ch R = 1 ,8000    ,625,625,625
BEGIN DESCRIPTION:
FIELD CREEK 14.0
END DESCRIPTION:
XS GIS Cut Line= 3
      2734855.72     10285103.12       2734455.6     10285013.66
      2733198.79      10285035.5
#Sta/Elev= 30
    4590 1347.35  4743.7 1340.46  4841.6  1333.3  4948.7 1330.62  4958.9 1328.97
    4977 1324.13  4982.4 1323.66  4982.9 1323.16  5011.8 1323.16  5012.3 1323.66
  5019.9  1326.4  5029.9 1331.58  5039.9 1335.14  5049.9 1336.08  5089.9 1334.64
  5199.9 1335.69    5340 1333.65    5680 1335.89    5820 1339.91    5860 1340.43
    5880 1342.05  5940.1 1343.08  5990.1 1345.39  6060.1 1347.07  6090.1 1349.52
  6100.1 1349.21  6120.1 1350.73  6150.1 1351.09  6210.1 1353.79    6257 1354.63
#Mann= 3 ,-1 , 0
    4590     .05       0  4982.4     .03       0  5012.3     .05       0
Bank Sta=4982.4,5012.3
XS Rating Curve= 0 ,0
Exp/Cntr=0.3,0.1

Type RM Length L Ch R = 1 ,7375    ,676,676,676
BEGIN DESCRIPTION:
Mapping XS bef0ad45
END DESCRIPTION:
XS GIS Cut Line= 4
      2735212.84      10284997.7      2734748.04     10284538.31
      2734153.54     10284257.27        2733388.     10284017.19
#Sta/Elev= 30
  4020.3 1357.11  4035.7 1357.32  4056.9 1356.11  4106.4 1355.16  4240.8 1349.49
  4269.1 1349.17    4361 1344.94  4488.2  1341.9  4650.8 1335.74  4763.6    1333
    4843 1329.95  4888.5 1329.99  4911.2 1328.86  4941.9 1328.67  4951.2 1327.52
    4974 1322.48  4986.1 1318.07  4993.3 1317.25  4993.8 1316.75  5023.2 1317.25
  5025.1 1328.11  5030.6 1331.79  5041.4 1333.77  5129.9 1333.45  5212.7 1331.74
    5434 1335.14  5538.8 1338.63  5930.9  1349.1  6060.7 1353.75  6133.7  1354.9
#Mann= 3 ,-1 , 0
  4020.3     .05       0  4993.3     .03       0  5023.2     .05       0
Bank Sta=4993.3,5023.2
XS Rating Curve= 0 ,0
Exp/Cntr=0.3,0.1

Type RM Length L Ch R = 1 ,6699    ,699,699,699
BEGIN DESCRIPTION:
Mapping XS 391f6a88
END DESCRIPTION:
XS GIS Cut Line= 4
      2736412.67     10284689.64      2735256.08     10284046.49
      2734612.93     10283797.88      2733851.92     10283469.86
#Sta/Elev= 30
  3318.6 1343.53  3489.4 1339.85  3711.3 1339.77  3944.6 1332.19  3954.9 1332.82
  4047.5 1331.45  4188.2 1331.56  4431.8 1335.95  4685.3 1331.35  4953.3 1330.93
    4964  1329.1  4969.8 1324.37  4970.5 1320.72    4971 1320.22  5000.4 1320.72
  5017.6  1321.2  5024.4 1325.01  5039.1 1327.01  5124.9 1328.46    5188 1331.13
  5253.5 1330.43    5327 1331.43  5491.8 1337.43  5502.5 1337.01    5677 1344.32
    5765  1350.6    5841 1354.18    5888 1354.36    6069 1345.66  6160.2 1342.36
#Mann= 3 ,-1 , 0
  3318.6     .05       0  4970.5     .03       0  5000.4     .05       0
Bank Sta=4970.5,5000.4
XS Rating Curve= 0 ,0
Exp/Cntr=0.3,0.1

Type RM Length L Ch R = 1 ,6000    ,1500,1500,1500
BEGIN DESCRIPTION:
FIELD CREEK 10.0
END DESCRIPTION:
XS GIS Cut Line= 3
      2737155.65      10284053.1      2735236.71       10283339.
      2734905.73     10283153.13
#Sta/Elev= 30
  2952.5  1367.4  2992.6 1364.99  3028.3 1364.28  3069.8 1361.11  3176.5 1356.14
  3194.4 1354.27  3199.7 1355.35  3224.7  1352.2  3335.4 1346.85  3635.3 1337.25
  3854.9 1327.49  3923.4 1325.38  4026.2 1327.47  4350.2 1329.51  4827.8 1328.12
  4883.1 1326.57  4958.4 1326.27  4968.8 1324.93  4979.8 1320.79  4989.3 1318.68
  4989.8 1318.18  5019.4 1318.68    5026 1322.03  5035.6 1323.52  5047.7  1327.3
  5085.4 1332.77  5128.7  1336.5  5231.4 1341.08  5312.4 1341.74  5379.6 1343.89
#Mann= 3 ,-1 , 0
  2952.5     .05       0  4989.3     .03       0  5019.4     .05       0
Bank Sta=4989.3,5019.4
XS Rating Curve= 0 ,0
Exp/Cntr=0.3,0.1

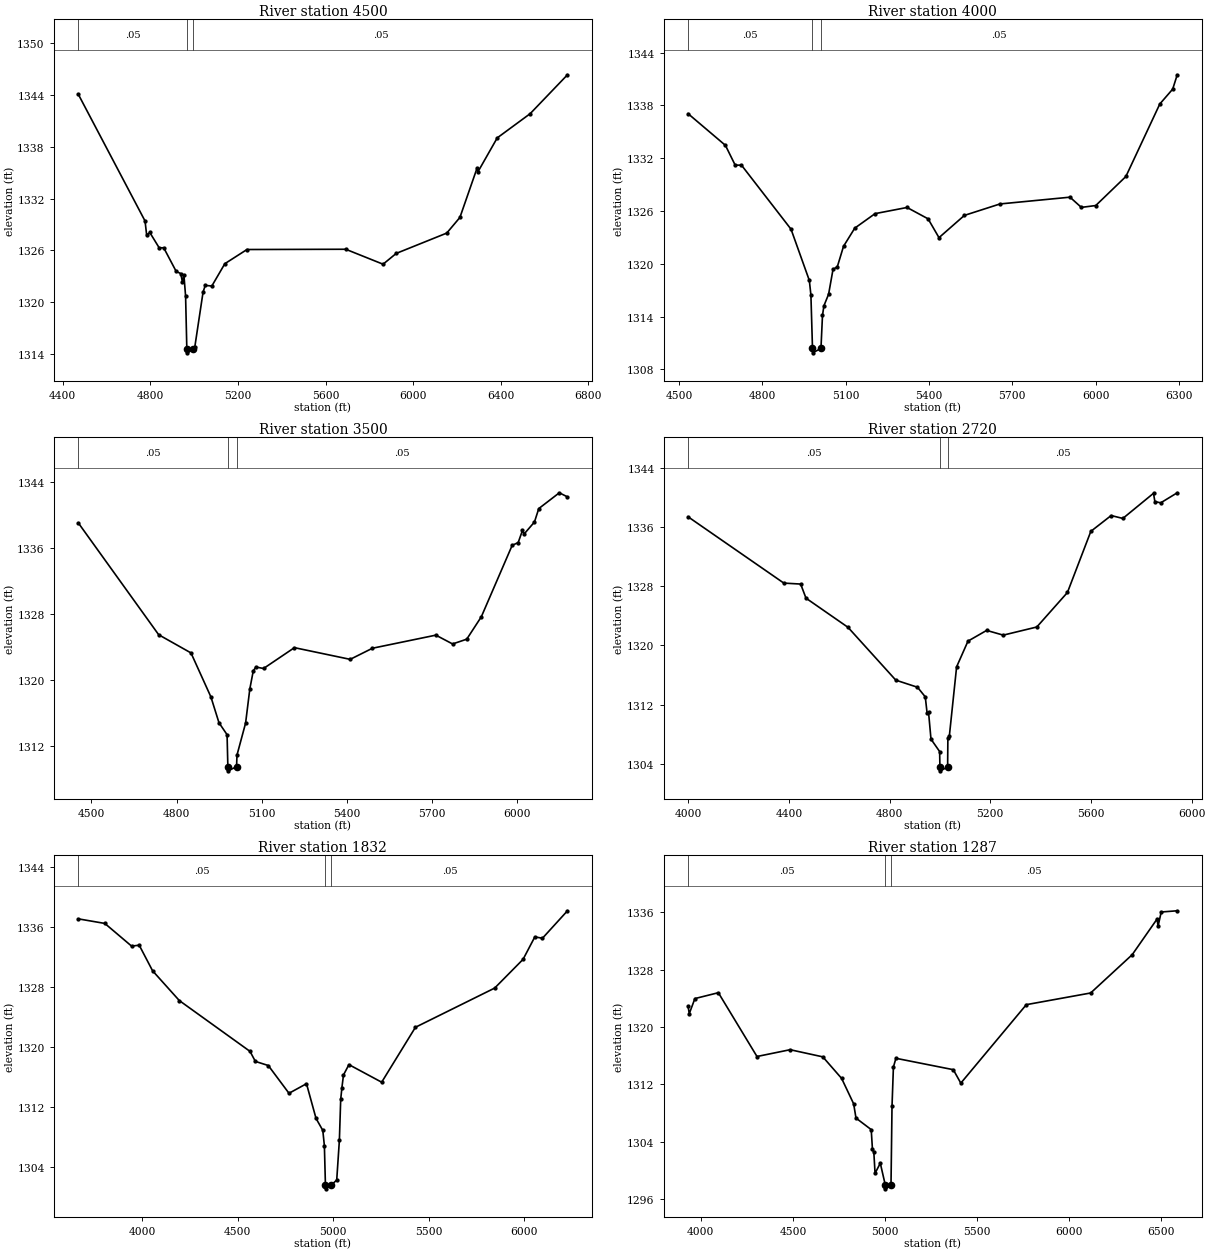
Type RM Length L Ch R = 1 ,4500    ,500,500,500
BEGIN DESCRIPTION:
FIELD CREEK 9.0
END DESCRIPTION:
XS GIS Cut Line= 3
      2736905.68     10282703.12      2736506.61      10283049.3
      2734805.67     10283153.11
#Sta/Elev= 30
  4471.7 1344.05  4776.2  1329.4  4783.7 1327.76  4797.9 1328.07  4840.7  1326.3
  4861.5  1326.3  4918.5 1323.56  4939.4 1323.32    4947 1322.31  4953.6 1323.15
  4961.3 1320.71  4966.9 1314.65  4967.4 1314.15  4997.3 1314.65    5003 1314.77
    5041 1321.17    5051 1321.95  5081.1 1321.88  5140.4 1324.46  5241.4  1326.1
  5692.2 1326.13  5862.5  1324.4  5922.6 1325.65  6153.1    1328  6213.2 1329.81
    6291 1335.48    6296 1335.11  6383.5 1339.01  6533.8 1341.81  6704.1 1346.31
#Mann= 3 ,-1 , 0
  4471.7     .05       0  4966.9     .03       0  4997.3     .05       0
Bank Sta=4966.9,4997.3
XS Rating Curve= 0 ,0
Exp/Cntr=0.3,0.1

Type RM Length L Ch R = 1 ,4000    ,500,500,500
BEGIN DESCRIPTION:
FIELD CREEK 8.0
END DESCRIPTION:
XS GIS Cut Line= 3
      2736705.65     10282403.13      2736292.55       10282622.
      2735055.64     10283003.13
#Sta/Elev= 30
  4532.5 1337.06    4667 1333.46  4702.2 1331.21  4724.8 1331.21  4903.3 1323.93
  4969.2 1318.11  4974.9 1316.45  4980.6 1310.38  4981.1 1309.88  5011.1 1310.38
  5016.6 1314.14  5021.8 1315.23  5038.6 1316.54  5054.5 1319.36    5070 1319.66
  5092.4 1321.99  5132.8 1324.05    5206  1325.7  5321.1  1326.4  5396.9 1325.11
  5436.2 1322.97  5527.7  1325.5  5655.9  1326.8    5908 1327.57  5948.9 1326.41
  6000.8 1326.62  6109.3 1329.92  6231.5 1338.16  6277.9 1339.85  6294.3 1341.48
#Mann= 3 ,-1 , 0
  4532.5     .05       0  4980.6     .04       0  5011.1     .05       0
Bank Sta=4980.6,5011.1
XS Rating Curve= 0 ,0
Exp/Cntr=0.3,0.1

Type RM Length L Ch R = 1 ,3500    ,780,780,780
BEGIN DESCRIPTION:
FIELD CREEK 7.0
END DESCRIPTION:
XS GIS Cut Line= 3
      2736355.71     10281903.09      2735944.81     10282262.95
      2734955.69     10282903.11
#Sta/Elev= 30
  4453.8 1339.08  4737.1  1325.5    4851 1323.29  4921.2 1317.95  4949.7 1314.81
  4978.2 1313.36    4981 1309.47  4981.5 1308.97  5011.6 1309.47  5013.2 1310.89
  5043.5 1314.77  5058.5 1318.94  5070.5  1321.1  5079.8 1321.58  5106.8  1321.4
  5215.6 1323.93  5412.2 1322.51  5490.7 1323.86  5714.2 1325.45  5773.2 1324.38
  5823.1 1324.96  5874.5 1327.68  5983.3 1336.36  6004.4 1336.69  6019.6 1338.17
  6025.5 1337.74  6061.8 1339.19    6077 1340.82  6149.5 1342.74  6178.2 1342.24
#Mann= 3 ,-1 , 0
  4453.8     .05       0    4981     .05       0  5011.6     .05       0
Bank Sta=4981,5011.6
XS Rating Curve= 0 ,0
Exp/Cntr=0.3,0.1

Type RM Length L Ch R = 1 ,2720    ,888,888,888
BEGIN DESCRIPTION:
Mapping XS 2e7305ce
END DESCRIPTION:
XS GIS Cut Line= 4
      2735996.52     10281517.12      2735299.31     10281960.31
       2735050.7     10282430.51      2734812.92     10282965.52
#Sta/Elev= 30
  3999.3 1337.41  4379.7 1328.44  4446.6 1328.31  4467.8  1326.4  4634.6 1322.46
  4824.6 1315.31  4910.8 1314.35  4941.7 1313.05  4949.1 1310.81  4954.8 1310.94
  4964.4 1307.33  4998.8 1305.65  4999.9 1303.54  5000.4 1303.04  5030.5 1303.54
  5031.5 1307.43  5037.2  1307.7  5066.2 1317.11  5111.4 1320.59  5185.6 1322.04
  5251.6  1321.4  5384.8  1322.5  5506.5 1327.17  5599.5 1335.44  5680.2 1337.58
  5726.7 1337.19  5848.5 1340.59  5853.9 1339.47  5877.2  1339.3  5942.8 1340.66
#Mann= 3 ,-1 , 0
  3999.3     .05       0  4999.9     .05       0  5030.5     .05       0
Bank Sta=4999.9,5030.5
XS Rating Curve= 0 ,0
Exp/Cntr=0.3,0.1

Type RM Length L Ch R = 1 ,1832    ,545,545,545
BEGIN DESCRIPTION:
Mapping XS c92bdb46
END DESCRIPTION:
XS GIS Cut Line= 4
      2735834.37     10281279.33      2734904.78     10281300.94
      2734294.06     10281760.34       2734002.2     10282576.46
#Sta/Elev= 30
  3665.4 1337.11  3804.1  1336.5  3944.2 1333.47  3984.2 1333.59  4054.2 1330.17
  4194.2 1326.19  4564.3  1319.4  4592.3 1318.06    4660 1317.51  4768.3  1313.8
  4859.9 1315.08  4909.9 1310.44  4945.3 1308.84  4953.6 1306.79  4959.1 1301.53
  4959.6 1301.03  4989.8 1301.53  5018.2 1302.21  5032.1 1307.51    5039 1312.97
  5045.3 1314.54  5053.6 1316.25  5082.1 1317.63  5253.5 1315.28  5430.2 1322.62
  5845.1 1327.86  5993.7  1331.7  6055.3  1334.7  6095.2 1334.52  6226.2 1338.19
#Mann= 3 ,-1 , 0
  3665.4     .05       0  4959.1     .03       0  4989.8     .05       0
Bank Sta=4959.1,4989.8
XS Rating Curve= 0 ,0
Exp/Cntr=0.3,0.1

Type RM Length L Ch R = 1 ,1287    ,438,438,438
BEGIN DESCRIPTION:
Mapping XS 66ca7dad
END DESCRIPTION:
XS GIS Cut Line= 5
      2735391.95     10280744.57      2734497.83     10280931.21
      2734341.58     10281109.16      2734172.31     10281920.79
      2733933.58     10282554.52
#Sta/Elev= 30
  3930.7 1322.91  3937.1 1321.86  3967.7 1323.97  4095.1 1324.79  4304.9 1315.88
    4485 1316.83  4662.4 1315.83  4764.6 1312.82  4829.9 1309.27  4842.6 1307.28
  4925.3 1305.67  4931.9 1302.94  4939.5 1302.51  4946.1 1299.57  4974.6 1300.98
    5002  1297.9  5002.5  1297.4  5032.7  1297.9  5038.2 1308.92  5045.8 1314.41
  5059.5 1315.63    5371 1314.04  5411.8 1312.16  5767.6 1323.12    6117 1324.75
  6342.7  1330.1  6477.7 1335.08  6483.1 1334.08  6500.2 1336.06  6587.2 1336.23
#Mann= 3 ,-1 , 0
  3930.7     .05       0    5002     .03       0  5032.7     .05       0
Bank Sta=5002,5032.7
XS Rating Curve= 0 ,0
Exp/Cntr=0.3,0.1

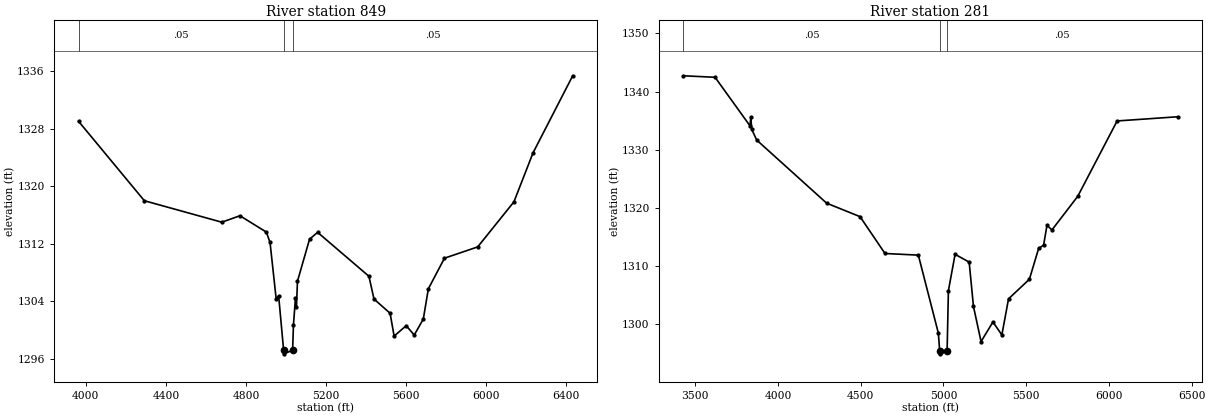
Type RM Length L Ch R = 1 ,849     ,568,568,568
BEGIN DESCRIPTION:
Mapping XS 4214ea38
END DESCRIPTION:
XS GIS Cut Line= 4
      2735357.16     10280275.84      2734740.88     10280484.16
      2734363.28     10280631.73      2732958.87     10280475.69
#Sta/Elev= 30
    3964 1329.05  4292.8 1317.99  4679.7    1315  4770.4  1315.9  4902.4 1313.62
  4920.7 1312.19  4951.3 1304.34  4963.7 1304.74  4988.6 1297.17  4989.6 1296.67
  5033.5 1297.17  5037.7 1300.65  5047.7 1304.41  5052.7 1303.19  5057.8 1306.78
  5118.1 1312.63  5158.4 1313.59  5414.9 1307.47  5440.1  1304.3  5520.6 1302.32
  5540.7 1299.14  5601.1 1300.59  5641.3 1299.29  5686.6 1301.52  5711.8 1305.73
  5792.3 1309.99  5958.3 1311.56  6139.4 1317.84    6235 1324.67    6433 1335.39
#Mann= 3 ,-1 , 0
    3964     .05       0  4988.6     .05       0  5033.5     .05       0
Bank Sta=4988.6,5033.5
XS Rating Curve= 0 ,0
Exp/Cntr=0.3,0.1

Type RM Length L Ch R = 1 ,281     ,0,0,0
BEGIN DESCRIPTION:
Mapping XS 2be318bf
END DESCRIPTION:
XS GIS Cut Line= 3
      2735645.18      10279960.6      2734220.05     10280128.26
      2732683.55     10280340.94
#Sta/Elev= 30
  3429.2 1342.71    3620 1342.45  3831.1  1334.1  3836.2 1335.62  3841.5  1333.5
  3871.7 1331.65  4294.6 1320.79    4496 1318.48    4647 1312.14  4848.4 1311.86
  4969.5 1298.43  4977.3 1295.38  4978.3 1294.88  5022.3 1295.38  5030.1 1305.74
  5070.5    1312  5155.6 1310.66  5181.5 1303.04  5227.4 1296.99  5299.2 1300.36
  5353.1 1298.13  5393.5 1304.34  5519.6 1307.71  5575.2    1313  5605.5 1313.59
  5625.7 1316.97    5656  1316.2  5811.8 1321.98  6049.7 1334.94  6415.3 1335.66
#Mann= 3 ,-1 , 0
  3429.2     .05       0  4977.3     .05       0  5022.3     .05       0
Bank Sta=4977.3,5022.3
XS Rating Curve= 0 ,0
Exp/Cntr=0.3,0.1
Stream Node=FIELD CREEK     ,Reach-1         , 0 , 0 ,Upstream end
Stream Node=FIELD CREEK     ,Reach-1         , 0 , 1 ,Downstream end

Chan Stop Cuts=-1
Use User Specified Reach Order=0
Composite Channel Slope=5