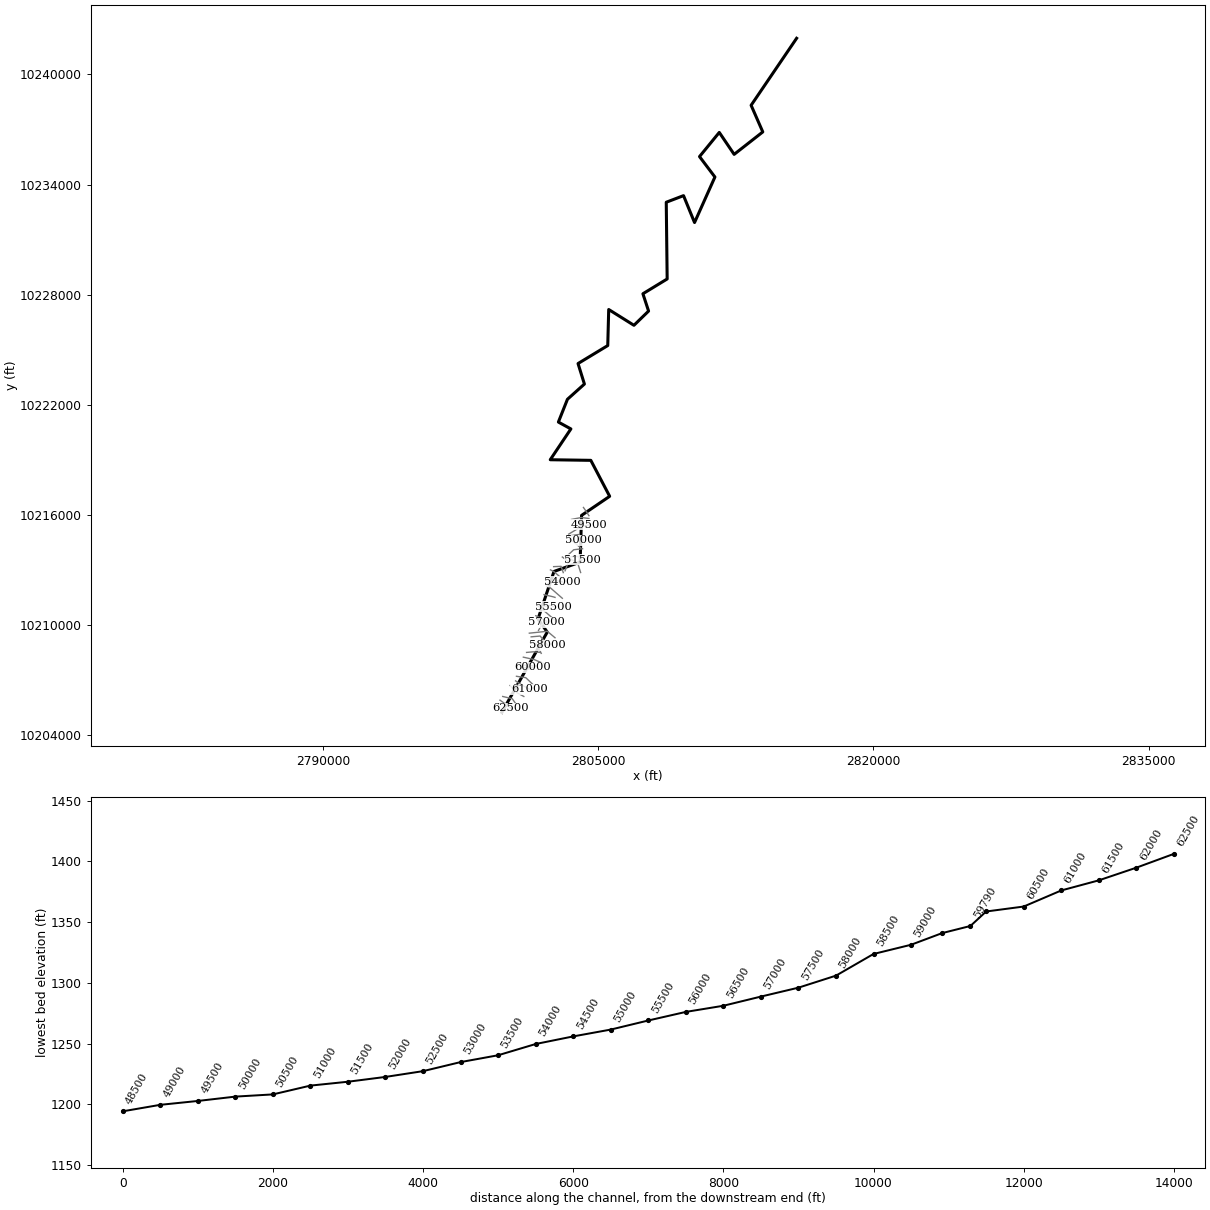
--- FLAG CREEK.prj (project) ---

Proj Title=FLAG CREEK Base Level Engineering
Current Plan=p01
Default Exp/Contr=0.3,0.1
English Units
Geom File=g01
Flow File=f01
Plan File=p01
BEGIN DESCRIPTION:
FLAG CREEK
END DESCRIPTION:

--- FLAG CREEK.p01 (plan) ---

Plan Title=Multiple Run
Short Identifier=Multiple
Geom File=g01
Flow File=f01
Subcritical Flow
K Sum by GR= 0
Std Step Tol= 0.01
Critical Tol= 0.01
Num of Std Step Trials= 20
Max Error Tol= 0.3
Flow Tol Ratio= 0.001
Split Flow NTrial= 30
Split Flow Tol= 0.02
Split Flow Ratio= 0.02
Log Output Level= 0
Friction Slope Method= 1
Unsteady Friction Slope Method= 2
Unsteady Bridges Friction Slope Method= 1
Parabolic Critical Depth
Global Vel Dist=  1 , 1 , 1
Global Log Level= 0
CheckData=True
Encroach Param= -1, 0, 0, 0
BEGIN DESCRIPTION:
Multiple Run
END DESCRIPTION:

--- FLAG CREEK.f01 (steady flow) ---

Flow Title=Multiple
Program Version=4.10
Number of Profiles= 7
Profile Names=10-year,25-year,50-year,1pct_min,100-year,1pct_plu,500-year
River Rch & RM=FLAG CREEK,Reach-1         ,62500
     495     814    1516     991    2123    4548    3071
River Rch & RM=FLAG CREEK,Reach-1         ,51500
     762    1298    2156    1552    3032    5924    4346
River Rch & RM=FLAG CREEK,Reach-1         ,42000
    1305    2284    4129    2432    5917   14391    8412
River Rch & RM=FLAG CREEK,Reach-1         ,36500
    1517    2679    4863    3950    6997   12395    9921
River Rch & RM=FLAG CREEK,Reach-1         ,33500
    1791    3204    5622    3975    8105   16528   11448
River Rch & RM=FLAG CREEK,Reach-1         ,27399
    2057    3708    6569    4853    9508   18630   13392
River Rch & RM=FLAG CREEK,Reach-1         ,24500
    2214    4012    7034    5254   10194   19778   14335
River Rch & RM=FLAG CREEK,Reach-1         ,21643
    2770    5104    8727    7528   12705   21444   17803
River Rch & RM=FLAG CREEK,Reach-1         ,11000
    3038    5646    9508    7996   13857   24016   19351
River Rch & RM=FLAG CREEK,Reach-1         ,6225
    3322    6229   10234    8363   14921   26620   20756
Boundary for River Rch & Prof#=FLAG CREEK,Reach-1         , 1
Up Type= 0
Dn Type= 3
Dn Slope=0.001
Boundary for River Rch & Prof#=FLAG CREEK,Reach-1         , 2
Up Type= 0
Dn Type= 3
Dn Slope=0.001
Boundary for River Rch & Prof#=FLAG CREEK,Reach-1         , 3
Up Type= 0
Dn Type= 3
Dn Slope=0.001
Boundary for River Rch & Prof#=FLAG CREEK,Reach-1         , 4
Up Type= 0
Dn Type= 3
Dn Slope=0.001
Boundary for River Rch & Prof#=FLAG CREEK,Reach-1         , 5
Up Type= 0
Dn Type= 3
Dn Slope=0.001
Boundary for River Rch & Prof#=FLAG CREEK,Reach-1         , 6
Up Type= 0
Dn Type= 3
Dn Slope=0.001
Boundary for River Rch & Prof#=FLAG CREEK,Reach-1         , 7
Up Type= 0
Dn Type= 3
Dn Slope=0.001
DSS Import GetInterval= 0
DSS Import GetPeak= 0
DSS Import FillOption= 0

--- FLAG CREEK.g01 (geometry) ---

Geom Title=Existing Conditions

River Reach=FLAG CREEK,Reach-1
Reach XY= 30
      2799760.00     10205239.00      2802232.75     10209610.00
      2801728.75     10210326.00      2802600.50     10212916.00
      2804024.00     10213426.00      2804102.75     10215971.00
      2805634.00     10217011.00      2804606.50     10218971.00
      2802395.50     10219004.00      2803520.50     10220683.00
      2802839.25     10221056.00      2803333.00     10222298.00
      2804257.75     10223128.00      2803910.50     10224246.00
      2805529.75     10225226.00      2805582.00     10227191.00
      2806957.50     10226330.00      2807755.00     10227105.00
      2807445.50     10228049.00      2808767.50     10228855.00
      2808718.00     10233036.00      2809659.50     10233396.00
      2810259.50     10231929.00      2811370.00     10234411.00
      2810530.50     10235524.00      2811607.50     10236841.00
      2812418.00     10235645.00      2813979.00     10236868.00
      2813343.00     10238320.00      2815822.50     10241971.00

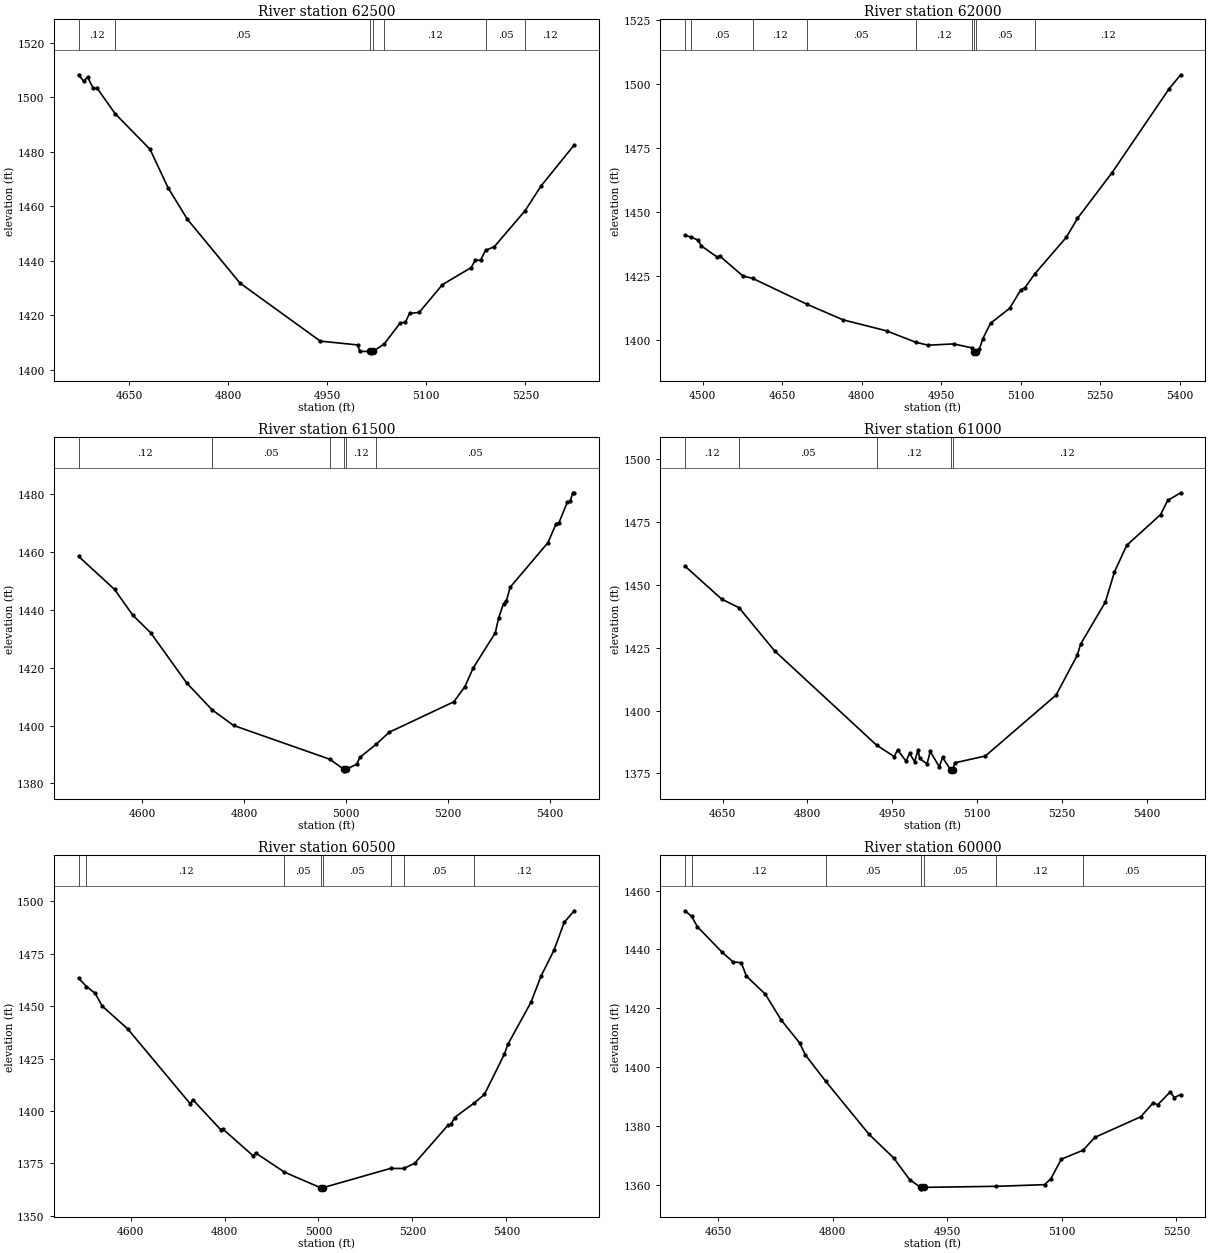
Type RM Length L Ch R = 1,62500,500,500,500
BEGIN DESCRIPTION:
FLAG CREEK 124.0
END DESCRIPTION:
XS GIS Cut Line= 3
      2799655.66     10205903.13      2800002.05     10205654.48
      2800255.65     10205453.14
#Sta/Elev= 30
  4573.6 1508.21  4581.0 1505.87  4587.2 1507.36  4595.7 1503.23  4601.9 1503.19
  4628.9 1493.92  4681.7 1480.86  4709.0 1466.74  4738.2 1455.19  4818.0 1431.73
  4939.5 1410.45  4996.0 1409.05  4999.2 1406.68  5015.4 1406.65  5015.7 1406.15
  5019.4 1406.65  5036.4 1409.49  5060.3 1417.08  5068.3 1417.41  5074.7 1420.66
  5089.1 1420.97  5124.4 1431.19  5167.7 1437.42  5174.0 1440.10  5182.1 1440.14
  5189.6 1443.77  5202.9 1445.10  5249.7 1458.38  5273.4 1467.32  5323.8 1482.43
#Mann=7,-1,0
  4573.6    0.12       0  4628.9    0.05       0  5015.4    0.03       0
  5019.4    0.05       0  5036.4    0.12       0  5189.6    0.05       0
  5249.7    0.12       0
Bank Sta=5015.4,5019.4
Exp/Cntr=0.3,0.1

Type RM Length L Ch R = 1,62000,500,500,500
BEGIN DESCRIPTION:
FLAG CREEK 123.0
END DESCRIPTION:
XS GIS Cut Line= 3
      2799805.71     10206103.11      2800324.66     10205981.54
      2800555.66     10205653.15
#Sta/Elev= 30
  4467.0 1440.69  4478.1 1440.04  4490.8 1438.88  4497.8 1436.54  4528.1 1432.12
  4533.2 1432.46  4575.7 1424.89  4594.4 1423.88  4696.9 1413.77  4764.8 1407.69
  4847.0 1403.38  4901.8 1398.93  4925.7 1397.77  4973.3 1398.28  5007.6 1396.75
  5011.4 1395.29  5011.7 1394.79  5015.4 1395.29  5022.1 1396.35  5028.3 1400.25
  5043.1 1406.37  5078.8 1412.14  5099.7 1419.23  5108.1 1420.31  5126.3 1425.61
  5185.9 1439.94  5206.9 1447.32  5272.2 1465.21  5379.3 1497.83  5401.5 1503.44
#Mann=9,-1,0
  4467.0    0.12       0  4478.1    0.05       0  4594.4    0.12       0
  4696.9    0.05       0  4901.8    0.12       0  5007.6    0.05       0
  5011.4    0.07       0  5015.4    0.05       0  5126.3    0.12       0
Bank Sta=5011.4,5015.4
Exp/Cntr=0.3,0.1

Type RM Length L Ch R = 1,61500,500,500,500
BEGIN DESCRIPTION:
FLAG CREEK 122.0
END DESCRIPTION:
XS GIS Cut Line= 3
      2800205.70     10206703.10      2800563.09     10206319.21
      2800955.65     10206103.13
#Sta/Elev= 30
  4475.5 1458.40  4546.1 1446.98  4581.8 1438.10  4616.9 1432.04  4687.8 1414.64
  4737.5 1405.42  4779.6 1400.03  4968.4 1388.37  4996.2 1384.86  4996.5 1384.36
  5000.2 1384.86  5021.6 1386.68  5027.3 1388.99  5060.0 1393.60  5085.2 1397.70
  5211.9 1408.20  5233.7 1413.45  5249.8 1419.83  5293.3 1432.02  5299.7 1437.07
  5309.4 1442.08  5315.1 1443.03  5322.6 1447.79  5396.5 1463.12  5412.6 1469.63
  5418.3 1470.05  5434.4 1477.02  5440.1 1477.38  5445.3 1480.37  5448.1 1480.37
#Mann=6,-1,0
  4475.5    0.12       0  4737.5    0.05       0  4968.4    0.12       0
  4996.2    0.07       0  5000.2    0.12       0  5060.0    0.05       0
Bank Sta=4996.2,5000.2
Exp/Cntr=0.3,0.1

Type RM Length L Ch R = 1,61000,500,500,500
BEGIN DESCRIPTION:
FLAG CREEK 121.0
END DESCRIPTION:
XS GIS Cut Line= 3
      2800505.66     10206953.13      2800853.77     10206724.99
      2801255.69     10206503.11
#Sta/Elev= 30
  4583.8 1457.46  4648.6 1444.33  4678.9 1440.98  4742.1 1423.74  4921.9 1386.29
  4953.2 1381.73  4959.1 1384.37  4974.2 1379.85  4980.2 1383.03  4989.3 1379.67
  4995.3 1384.43  4998.2 1380.95  5011.1 1378.79  5016.8 1383.74  5032.8 1377.63
  5038.5 1381.37  5052.6 1376.54  5052.9 1376.04  5056.6 1376.54  5060.3 1379.23
  5114.2 1381.95  5239.1 1406.19  5276.3 1421.96  5282.6 1426.52  5326.2 1443.23
  5342.2 1455.21  5364.0 1465.81  5423.6 1477.98  5436.2 1483.62  5459.1 1486.68
#Mann=5,-1,0
  4583.8    0.12       0  4678.9    0.05       0  4921.9    0.12       0
  5052.6    0.07       0  5056.6    0.12       0
Bank Sta=5052.6,5056.6
Exp/Cntr=0.3,0.1

Type RM Length L Ch R = 1,60500,500,500,500
BEGIN DESCRIPTION:
FLAG CREEK 120.0
END DESCRIPTION:
XS GIS Cut Line= 3
      2800555.67     10207203.11      2801060.93     10207128.11
      2801455.70     10206753.09
#Sta/Elev= 30
  4489.2 1463.32  4505.9 1459.39  4523.9 1456.25  4539.8 1449.98  4593.4 1439.23
  4727.2 1403.34  4732.2 1405.43  4791.6 1391.06  4796.6 1391.32  4861.0 1378.54
  4866.0 1379.98  4927.5 1370.78  5004.7 1363.31  5005.0 1362.81  5008.7 1363.31
  5153.7 1372.58  5181.5 1372.53  5204.9 1375.02  5275.7 1393.16  5282.6 1393.65
  5289.8 1396.85  5331.5 1403.77  5353.4 1407.87  5395.8 1427.09  5403.1 1431.71
  5452.5 1451.87  5473.9 1464.33  5502.2 1477.05  5523.2 1489.99  5544.5 1495.54
#Mann=8,-1,0
  4489.2    0.05       0  4505.9    0.12       0  4927.5    0.05       0
  5004.7    0.05       0  5008.7    0.05       0  5153.7    0.12       0
  5181.5    0.05       0  5331.5    0.12       0
Bank Sta=5004.7,5008.7
Exp/Cntr=0.3,0.1

Type RM Length L Ch R = 1,60000,210,210,210
BEGIN DESCRIPTION:
FLAG CREEK 119.0
END DESCRIPTION:
XS GIS Cut Line= 3
      2800855.68     10207703.11      2801230.19     10207582.99
      2801455.69     10207703.11
#Sta/Elev= 30
  4606.7 1453.14  4615.2 1451.24  4622.8 1447.74  4654.9 1439.13  4669.7 1435.74
  4680.2 1435.54  4687.0 1430.94  4711.7 1424.83  4732.7 1415.98  4756.5 1408.32
  4764.2 1404.19  4790.7 1395.28  4847.6 1377.22  4879.7 1369.24  4900.8 1361.83
  4915.1 1359.23  4915.4 1358.73  4919.1 1359.23  5014.4 1359.59  5077.3 1360.15
  5085.5 1362.10  5099.3 1368.81  5127.8 1371.84  5143.2 1376.21  5203.4 1383.21
  5219.7 1388.00  5225.4 1387.25  5241.7 1391.59  5247.3 1389.74  5255.5 1390.73
#Mann=7,-1,0
  4606.7    0.05       0  4615.2    0.12       0  4790.7    0.05       0
  4915.1    0.03       0  4919.1    0.05       0  5014.4    0.12       0
  5127.8    0.05       0
Bank Sta=4915.1,4919.1
Exp/Cntr=0.3,0.1

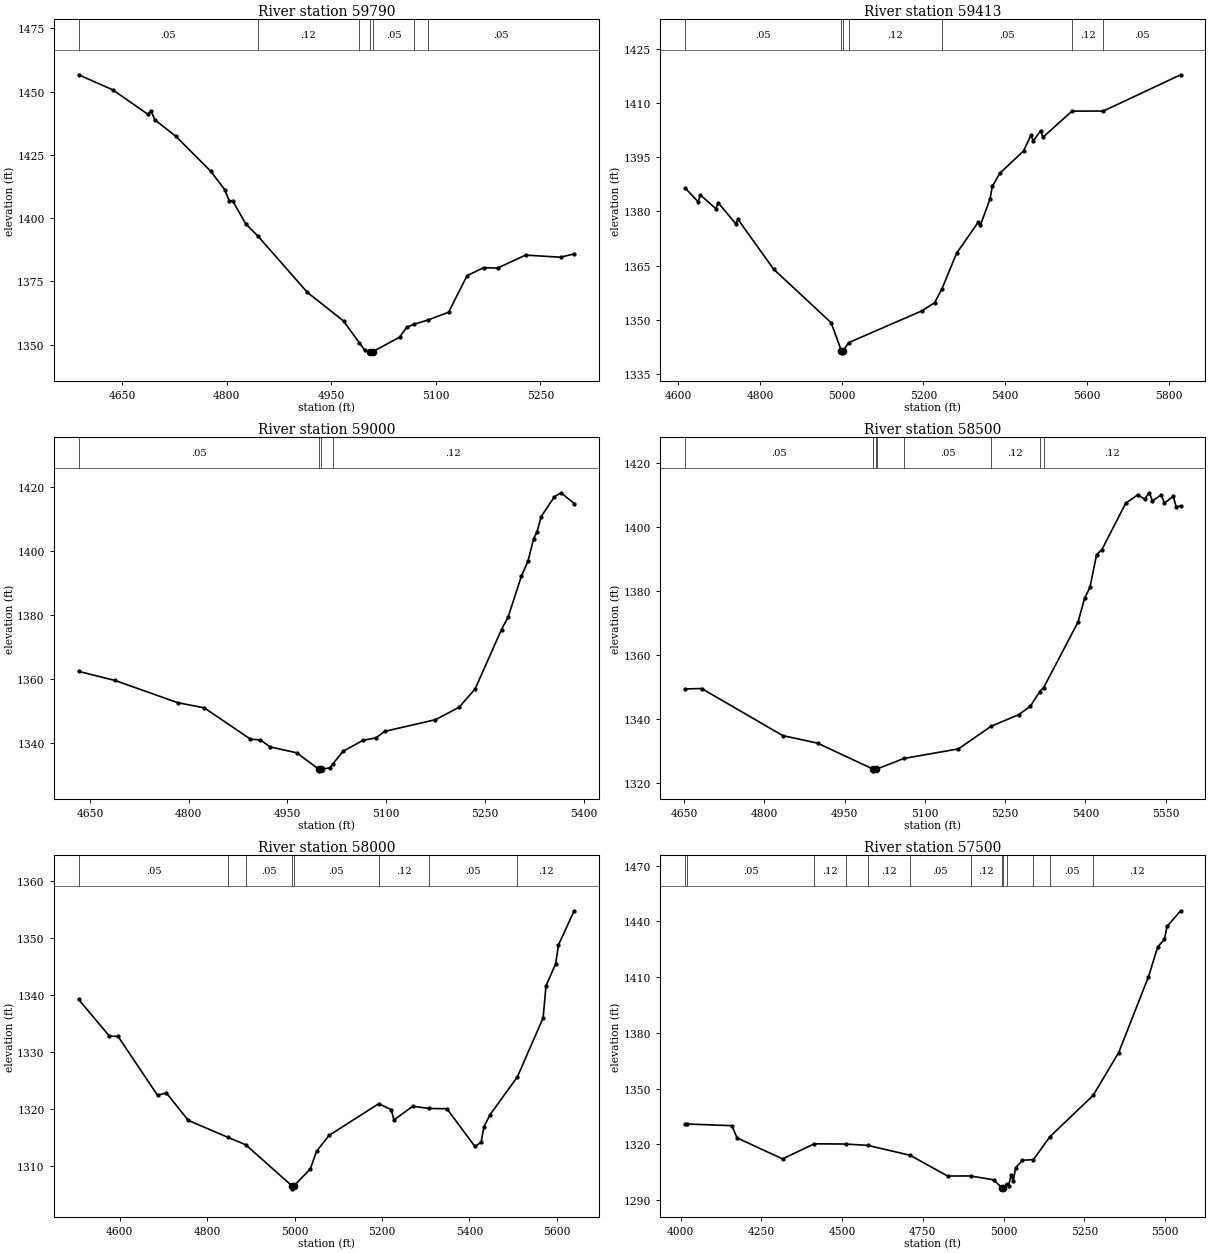
Type RM Length L Ch R = 1,59790,377,377,377
BEGIN DESCRIPTION:
Mapping XS 0aff4e2c
END DESCRIPTION:
XS GIS Cut Line= 2
      2800836.88     10207827.23      2801545.23     10207764.73
#Sta/Elev= 30
  4587.3 1456.61  4636.3 1450.66  4686.3 1441.08  4691.3 1442.40  4696.5 1438.85
  4726.6 1432.36  4776.8 1418.54  4796.9 1411.26  4803.4 1406.84  4808.4 1406.86
  4827.0 1397.78  4844.1 1393.06  4915.5 1370.69  4967.6 1359.36  4989.8 1350.85
  4997.7 1347.92  5005.7 1347.31  5006.0 1346.81  5009.7 1347.31  5047.9 1353.00
  5057.9 1356.85  5068.9 1358.13  5089.3 1359.83  5118.2 1362.85  5144.7 1377.28
  5168.3 1380.44  5188.4 1380.28  5228.6 1385.40  5278.8 1384.57  5298.4 1385.88
#Mann=7,-1,0
  4587.3    0.05       0  4844.1    0.12       0  4989.8    0.05       0
  5005.7    0.05       0  5009.7    0.05       0  5068.9    0.12       0
  5089.3    0.05       0
Bank Sta=5005.7,5009.7
Exp/Cntr=0.3,0.1

Type RM Length L Ch R = 1,59413,413,413,413
BEGIN DESCRIPTION:
Mapping XS f20877ed
END DESCRIPTION:
XS GIS Cut Line= 3
      2800930.03     10208245.23      2801516.00     10208115.02
      2802080.22     10207876.31
#Sta/Elev= 30
  4616.8 1386.48  4648.9 1382.64  4654.0 1384.57  4692.4 1380.73  4697.6 1382.44
  4741.1 1376.55  4746.2 1377.82  4833.3 1364.07  4974.2 1349.28  4999.6 1341.44
  4999.9 1340.94  5003.6 1341.44  5017.0 1343.75  5196.3 1352.54  5227.6 1354.80
  5245.6 1358.66  5281.3 1368.44  5334.1 1377.00  5339.5 1376.18  5363.2 1383.45
  5368.7 1386.93  5386.9 1390.52  5445.1 1396.70  5463.4 1401.06  5468.8 1399.48
  5487.1 1402.30  5492.5 1400.49  5563.9 1407.71  5640.7 1407.74  5829.7 1417.75
#Mann=7,-1,0
  4616.8    0.05       0  4999.6    0.03       0  5003.6    0.05       0
  5017.0    0.12       0  5245.6    0.05       0  5563.9    0.12       0
  5640.7    0.05       0
Bank Sta=4999.6,5003.6
Exp/Cntr=0.3,0.1

Type RM Length L Ch R = 1,59000,500,500,500
BEGIN DESCRIPTION:
FLAG CREEK 117.0
END DESCRIPTION:
XS GIS Cut Line= 3
      2801105.69     10208503.11      2801471.38     10208536.40
      2801855.64     10208503.12
#Sta/Elev= 30
  4632.8 1362.42  4688.0 1359.59  4783.4 1352.64  4823.6 1351.04  4893.9 1341.25
  4908.8 1341.01  4924.0 1338.82  4964.2 1336.99  4997.7 1331.86  4997.9 1331.36
  5001.7 1331.86  5014.4 1332.30  5018.7 1333.44  5034.4 1337.43  5064.5 1340.86
  5084.6 1341.66  5097.8 1343.68  5175.0 1347.34  5211.0 1351.23  5235.2 1356.94
  5275.3 1375.50  5285.4 1379.42  5305.4 1392.10  5315.5 1396.81  5324.2 1403.91
  5329.2 1405.94  5335.6 1410.76  5355.6 1416.94  5365.7 1418.20  5385.7 1414.84
#Mann=4,-1,0
  4632.8    0.05       0  4997.7    0.05       0  5001.7    0.05       0
  5018.7    0.12       0
Bank Sta=4997.7,5001.7
Exp/Cntr=0.3,0.1

Type RM Length L Ch R = 1,58500,500,500,500
BEGIN DESCRIPTION:
FLAG CREEK 116.0
END DESCRIPTION:
XS GIS Cut Line= 3
      2801305.67     10209053.11      2801643.27     10208968.26
      2801905.67     10208453.14
#Sta/Elev= 30
  4651.9 1349.39  4682.8 1349.52  4834.4 1334.80  4899.4 1332.44  5003.8 1324.28
  5004.0 1323.78  5007.8 1324.28  5011.5 1324.43  5060.6 1327.64  5162.9 1330.65
  5223.7 1337.70  5275.1 1341.31  5297.3 1343.98  5314.5 1348.53  5322.0 1349.80
  5386.3 1370.29  5398.6 1377.74  5408.5 1381.11  5421.0 1391.39  5430.8 1392.92
  5475.3 1407.41  5497.5 1410.04  5510.8 1408.76  5519.7 1410.72  5525.3 1408.16
  5542.0 1410.10  5547.6 1407.47  5564.2 1409.59  5569.8 1406.35  5578.1 1406.56
#Mann=8,-1,0
  4651.9    0.05       0  5003.8    0.05       0  5007.8    0.05       0
  5011.5    0.12       0  5060.6    0.05       0  5223.7    0.12       0
  5314.5    0.05       0  5322.0    0.12       0
Bank Sta=5003.8,5007.8
Exp/Cntr=0.3,0.1

Type RM Length L Ch R = 1,58000,500,500,500
BEGIN DESCRIPTION:
FLAG CREEK 115.0
END DESCRIPTION:
XS GIS Cut Line= 3
      2801355.73     10209353.12      2801848.06     10209396.08
      2802255.71     10208903.09
#Sta/Elev= 30
  4505.8 1339.20  4576.0 1332.78  4596.1 1332.70  4686.4 1322.37  4706.5 1322.80
  4756.7 1317.97  4848.0 1314.97  4888.1 1313.69  4994.3 1306.45  4994.5 1305.95
  4998.3 1306.45  5035.9 1309.44  5050.2 1312.55  5078.9 1315.34  5192.6 1320.90
  5220.9 1319.85  5227.4 1318.05  5270.4 1320.45  5307.6 1320.06  5348.5 1320.01
  5412.4 1313.40  5426.7 1314.10  5433.2 1316.86  5447.5 1319.00  5509.6 1325.59
  5568.7 1335.98  5575.2 1341.58  5597.3 1345.45  5603.8 1348.77  5639.7 1354.77
#Mann=8,-1,0
  4505.8    0.05       0  4848.0    0.12       0  4888.1    0.05       0
  4994.3    0.05       0  4998.3    0.05       0  5192.6    0.12       0
  5307.6    0.05       0  5509.6    0.12       0
Bank Sta=4994.3,4998.3
Exp/Cntr=0.3,0.1

Type RM Length L Ch R = 1,57500,500,500,500
BEGIN DESCRIPTION:
FLAG CREEK 114.0
END DESCRIPTION:
XS GIS Cut Line= 3
      2801255.70     10209553.11      2802236.24     10209655.83
      2802655.66     10209303.14
#Sta/Elev= 30
  4014.1 1330.70  4019.6 1330.94  4159.0 1330.05  4175.0 1323.45  4315.7 1312.17
  4414.0 1320.29  4512.9 1320.16  4580.4 1319.41  4710.5 1314.12  4826.7 1302.94
  4897.6 1302.99  4969.3 1300.89  4995.2 1296.55  4995.5 1296.05  4999.2 1296.55
  5009.6 1298.84  5015.4 1297.64  5023.2 1303.35  5029.7 1300.50  5037.5 1307.46
  5058.3 1311.41  5092.4 1311.80  5143.4 1324.12  5277.3 1346.38  5356.2 1369.38
  5448.5 1410.25  5477.1 1426.28  5498.0 1430.38  5505.8 1437.28  5548.0 1445.71
#Mann=13,-1,0
  4014.1    0.12       0  4019.6    0.05       0  4414.0    0.12       0
  4512.9    0.05       0  4580.4    0.12       0  4710.5    0.05       0
  4897.6    0.12       0  4995.2    0.07       0  4999.2    0.12       0
  5009.6    0.05       0  5092.4    0.12       0  5143.4    0.05       0
  5277.3    0.12       0
Bank Sta=4995.2,4999.2
Exp/Cntr=0.3,0.1

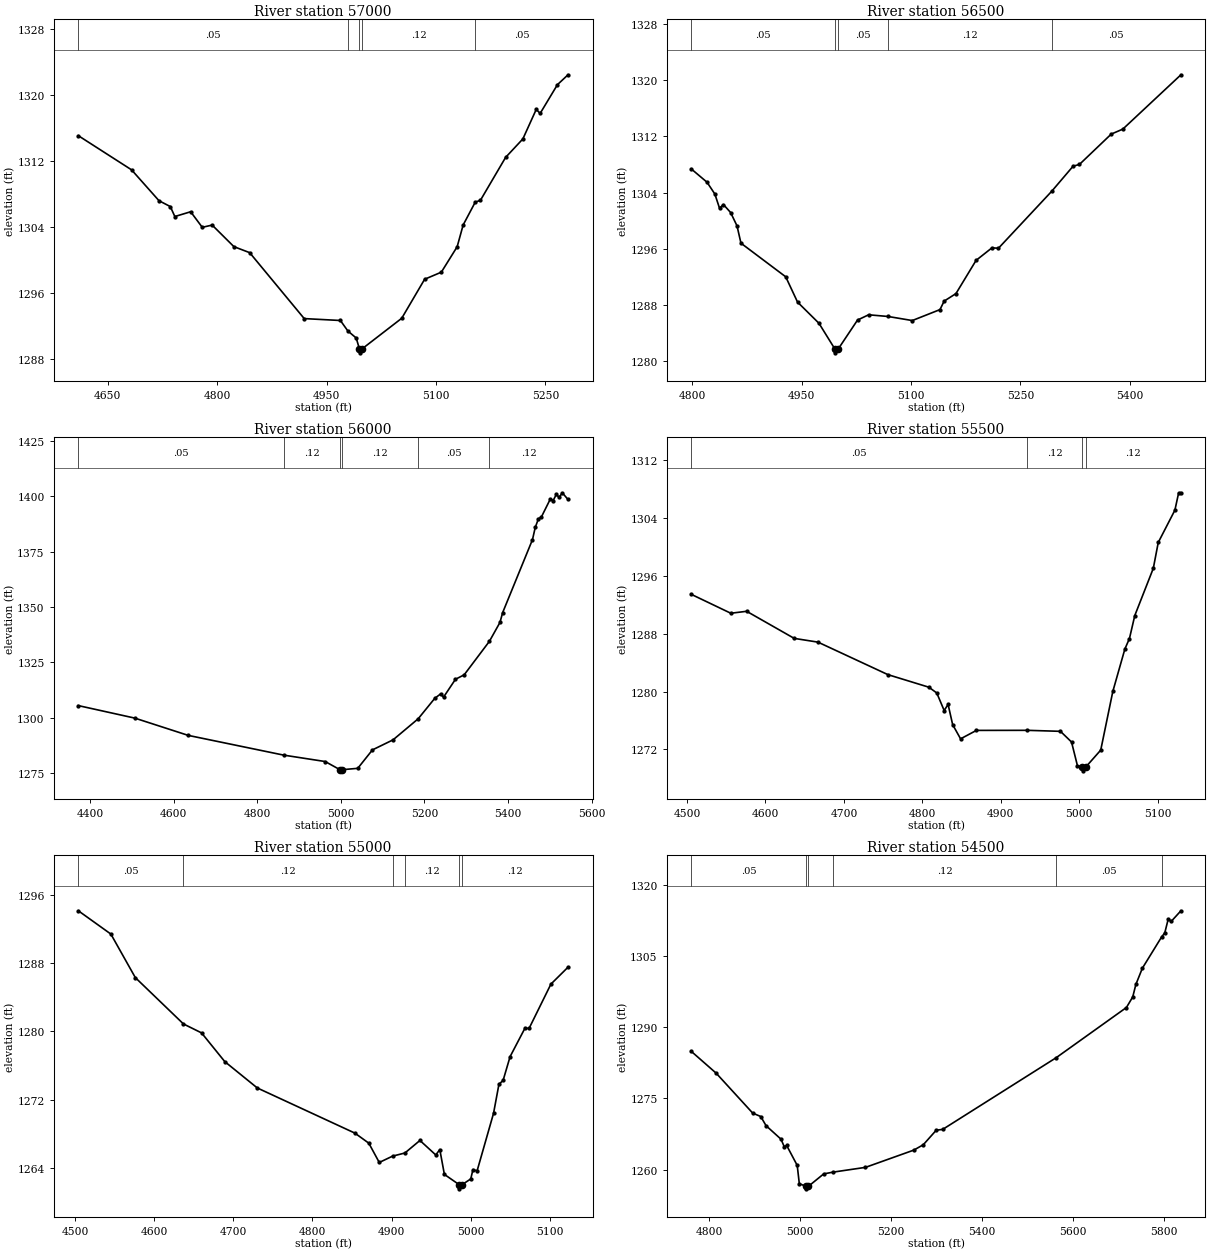
Type RM Length L Ch R = 1,57000,500,500,500
BEGIN DESCRIPTION:
FLAG CREEK 113.0
END DESCRIPTION:
XS GIS Cut Line= 3
      2801755.70     10209703.13      2801946.90     10210043.50
      2802205.65     10210153.10
#Sta/Elev= 30
  4609.6 1315.09  4682.6 1310.94  4720.2 1307.19  4735.7 1306.48  4741.9 1305.27
  4763.6 1305.85  4779.5 1303.96  4793.1 1304.23  4822.9 1301.61  4844.5 1300.88
  4919.3 1292.87  4968.9 1292.64  4979.2 1291.36  4990.6 1290.51  4994.9 1289.21
  4995.2 1288.71  4998.9 1289.21  5053.0 1292.91  5084.4 1297.65  5107.3 1298.51
  5129.0 1301.60  5137.2 1304.24  5153.8 1307.02  5160.9 1307.24  5195.4 1312.45
  5219.1 1314.70  5237.4 1318.28  5242.8 1317.80  5266.5 1321.29  5281.0 1322.49
#Mann=5,-1,0
  4609.6    0.05       0  4979.2    0.12       0  4994.9    0.07       0
  4998.9    0.12       0  5153.8    0.05       0
Bank Sta=4994.9,4998.9
Exp/Cntr=0.3,0.1

Type RM Length L Ch R = 1,56500,500,500,500
BEGIN DESCRIPTION:
FLAG CREEK 112.0
END DESCRIPTION:
XS GIS Cut Line= 3
      2801605.70     10210503.11      2801792.40     10210427.06
      2802205.72     10210203.09
#Sta/Elev= 30
  4798.4 1307.36  4820.0 1305.47  4830.8 1303.78  4837.2 1301.76  4842.6 1302.28
  4852.4 1301.15  4861.2 1299.24  4866.6 1296.78  4928.0 1291.99  4944.2 1288.39
  4973.6 1285.37  4995.7 1281.66  4995.9 1281.16  4999.7 1281.66  5026.5 1285.83
  5041.7 1286.58  5068.3 1286.34  5101.6 1285.76  5139.6 1287.32  5145.3 1288.53
  5161.5 1289.60  5189.1 1294.33  5210.9 1296.12  5219.8 1296.06  5292.9 1304.18
  5322.2 1307.75  5330.8 1307.99  5374.5 1312.32  5390.4 1313.03  5470.1 1320.77
#Mann=5,-1,0
  4798.4    0.05       0  4995.7    0.03       0  4999.7    0.05       0
  5068.3    0.12       0  5292.9    0.05       0
Bank Sta=4995.7,4999.7
Exp/Cntr=0.3,0.1

Type RM Length L Ch R = 1,56000,500,500,500
BEGIN DESCRIPTION:
FLAG CREEK 111.0
END DESCRIPTION:
XS GIS Cut Line= 3
      2801705.69     10211053.10      2802193.56     10210657.51
      2802605.65     10210303.14
#Sta/Elev= 30
  4371.9 1305.54  4507.0 1299.90  4634.8 1292.10  4863.3 1283.19  4962.5 1280.30
  4998.0 1276.60  4998.3 1276.10  5002.0 1276.60  5040.4 1277.23  5075.6 1285.56
  5124.9 1290.09  5185.0 1299.60  5224.8 1308.85  5239.0 1310.86  5245.6 1309.34
  5274.2 1317.43  5295.0 1319.43  5355.4 1334.56  5380.6 1343.06  5387.2 1347.56
  5458.5 1380.48  5465.1 1385.98  5472.8 1389.91  5479.4 1390.53  5501.3 1398.84
  5507.9 1398.09  5515.6 1400.88  5522.2 1399.49  5529.8 1401.60  5543.5 1398.57
#Mann=6,-1,0
  4371.9    0.05       0  4863.3    0.12       0  4998.0    0.07       0
  5002.0    0.12       0  5185.0    0.05       0  5355.4    0.12       0
Bank Sta=4998,5002
Exp/Cntr=0.3,0.1

Type RM Length L Ch R = 1,55500,500,500,500
BEGIN DESCRIPTION:
FLAG CREEK 110.0
END DESCRIPTION:
XS GIS Cut Line= 3
      2801955.73     10211003.12      2802445.52     10211071.26
      2802555.65     10211003.13
#Sta/Elev= 30
  4505.5 1293.47  4555.9 1290.85  4576.1 1291.12  4636.7 1287.37  4667.0 1286.85
  4756.1 1282.35  4808.3 1280.61  4818.4 1279.81  4827.8 1277.38  4832.8 1278.23
  4838.6 1275.43  4848.7 1273.46  4868.9 1274.63  4933.7 1274.64  4976.0 1274.50
  4990.1 1273.02  4997.6 1269.75  5004.0 1269.53  5004.3 1269.03  5008.0 1269.53
  5027.3 1271.90  5042.7 1280.02  5058.1 1285.91  5063.9 1287.35  5070.7 1290.53
  5094.3 1297.07  5100.6 1300.65  5121.8 1305.12  5126.6 1307.53  5129.5 1307.53
#Mann=4,-1,0
  4505.5    0.05       0  4933.7    0.12       0  5004.0    0.07       0
  5008.0    0.12       0
Bank Sta=5004,5008
Exp/Cntr=0.3,0.1

Type RM Length L Ch R = 1,55000,500,500,500
BEGIN DESCRIPTION:
FLAG CREEK 109.0
END DESCRIPTION:
XS GIS Cut Line= 3
      2802055.65     10211653.12      2802538.13     10211538.97
      2802655.68     10211503.11
#Sta/Elev= 30
  4504.2 1294.14  4545.3 1291.41  4576.2 1286.31  4637.0 1280.88  4659.9 1279.83
  4689.2 1276.47  4730.3 1273.38  4853.6 1268.09  4871.2 1266.91  4884.4 1264.65
  4901.2 1265.39  4916.8 1265.76  4935.8 1267.23  4955.8 1265.53  4960.9 1266.16
  4966.7 1263.25  4985.2 1262.06  4985.5 1261.56  4989.2 1262.06  5000.0 1262.72
  5002.8 1263.82  5008.0 1263.66  5028.8 1270.41  5035.6 1273.81  5040.9 1274.27
  5049.7 1277.05  5068.4 1280.37  5073.7 1280.36  5101.3 1285.55  5122.9 1287.53
#Mann=6,-1,0
  4504.2    0.05       0  4637.0    0.12       0  4901.2    0.05       0
  4916.8    0.12       0  4985.2    0.07       0  4989.2    0.12       0
Bank Sta=4985.2,4989.2
Exp/Cntr=0.3,0.1

Type RM Length L Ch R = 1,54500,500,500,500
BEGIN DESCRIPTION:
FLAG CREEK 108.0
END DESCRIPTION:
XS GIS Cut Line= 3
      2802205.65     10212103.13      2802424.03     10212004.31
      2803055.66     10211453.14
#Sta/Elev= 30
  4760.3 1284.94  4815.2 1280.33  4895.6 1271.91  4913.3 1271.19  4925.0 1269.26
  4957.9 1266.41  4965.0 1264.83  4970.4 1265.08  4993.6 1260.88  4998.2 1257.03
  5013.8 1256.44  5014.0 1255.94  5017.8 1256.44  5051.9 1259.09  5072.9 1259.47
  5143.9 1260.47  5250.3 1264.11  5271.1 1265.24  5299.6 1268.30  5313.9 1268.48
  5563.9 1283.61  5718.3 1294.18  5732.2 1296.41  5739.1 1299.04  5753.4 1302.47
  5795.7 1309.05  5802.7 1309.91  5810.3 1312.82  5817.0 1312.35  5838.3 1314.58
#Mann=6,-1,0
  4760.3    0.05       0  5013.8    0.05       0  5017.8    0.05       0
  5072.9    0.12       0  5563.9    0.05       0  5795.7    0.12       0
Bank Sta=5013.8,5017.8
Exp/Cntr=0.3,0.1

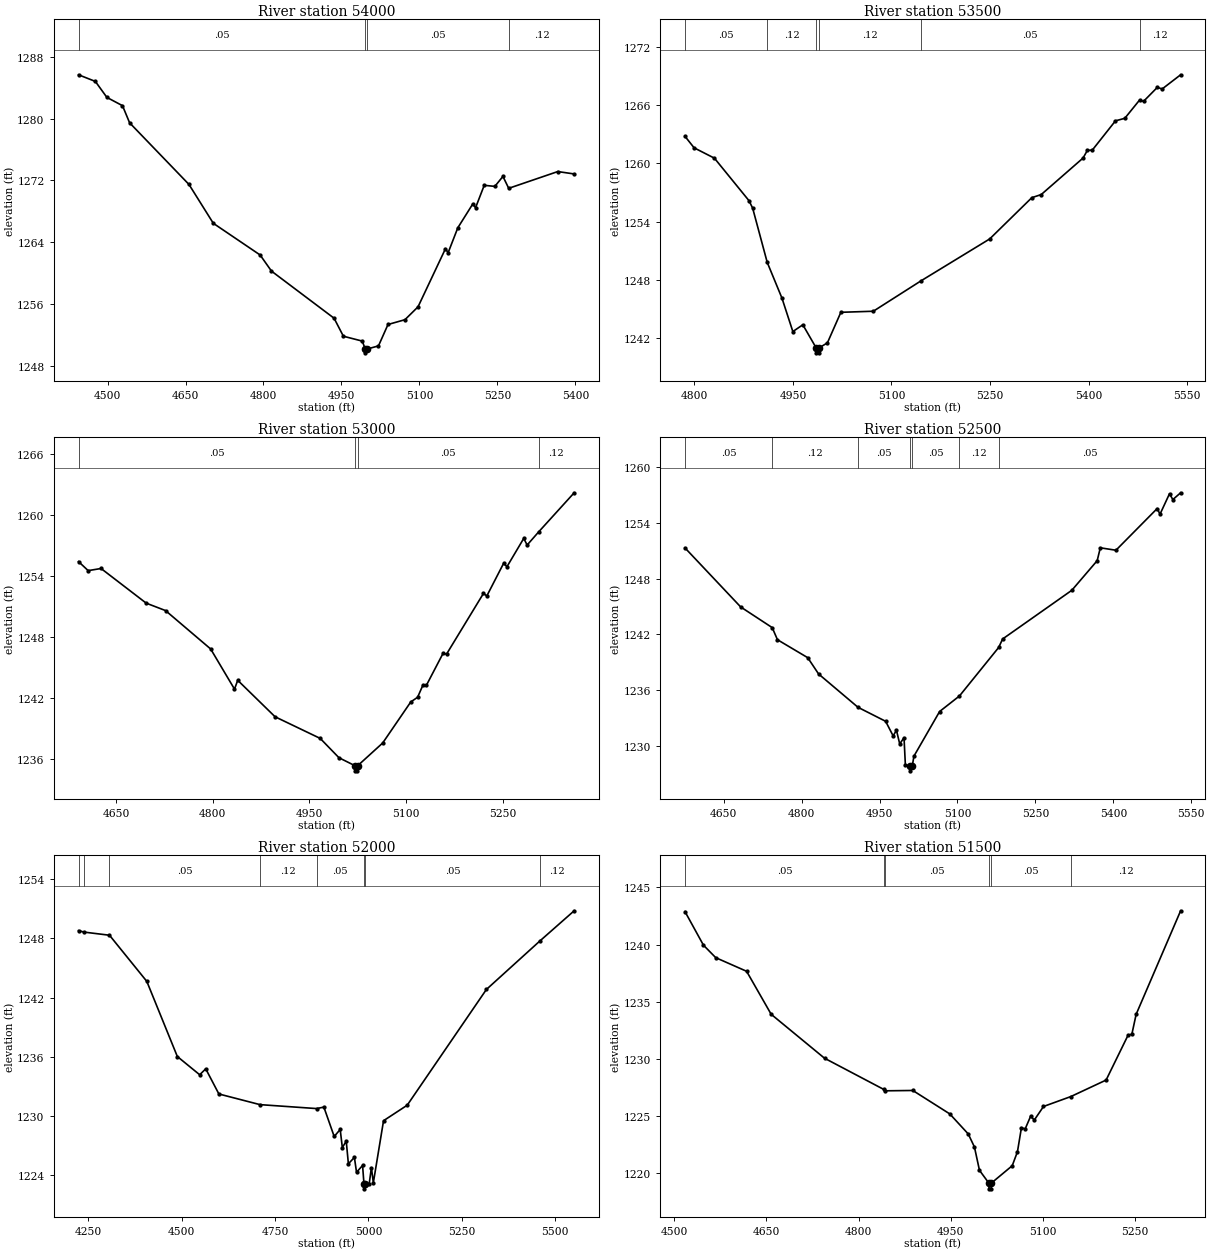
Type RM Length L Ch R = 1,54000,500,500,500
BEGIN DESCRIPTION:
FLAG CREEK 107.0
END DESCRIPTION:
XS GIS Cut Line= 3
      2802155.65     10212203.10      2802664.84     10212425.89
      2803055.72     10212353.11
#Sta/Elev= 30
  4444.2 1285.68  4476.6 1284.82  4498.8 1282.75  4528.8 1281.68  4542.5 1279.46
  4656.7 1271.48  4703.5 1266.45  4793.5 1262.35  4815.4 1260.26  4935.8 1254.16
  4953.7 1251.83  4990.0 1251.20  4995.7 1250.18  4996.0 1249.68  4999.7 1250.18
  5021.2 1250.58  5039.5 1253.35  5072.1 1253.97  5097.3 1255.64  5150.1 1263.17
  5155.1 1262.63  5173.8 1265.87  5202.8 1268.98  5207.9 1268.46  5224.6 1271.37
  5245.0 1271.23  5260.6 1272.52  5271.7 1270.98  5366.1 1273.15  5397.6 1272.84
#Mann=4,-1,0
  4444.2    0.05       0  4995.7    0.05       0  4999.7    0.05       0
  5271.7    0.12       0
Bank Sta=4995.7,4999.7
Exp/Cntr=0.3,0.1

Type RM Length L Ch R = 1,53500,500,500,500
BEGIN DESCRIPTION:
FLAG CREEK 106.0
END DESCRIPTION:
XS GIS Cut Line= 3
      2802405.68     10213003.11      2802596.84     10212906.24
      2803005.66     10212553.14
#Sta/Elev= 30
  4785.7 1262.81  4799.6 1261.62  4830.5 1260.55  4883.1 1256.16  4888.7 1255.39
  4910.9 1249.78  4933.3 1246.09  4949.9 1242.63  4965.1 1243.33  4985.5 1240.93
  4985.7 1240.43  4989.2 1240.43  4989.5 1240.93  5002.5 1241.46  5023.0 1244.62
  5072.4 1244.73  5145.2 1247.88  5249.5 1252.20  5313.7 1256.47  5328.0 1256.79
  5391.6 1260.56  5398.2 1261.35  5405.8 1261.39  5441.0 1264.41  5455.2 1264.67
  5477.6 1266.55  5483.7 1266.42  5504.6 1267.86  5512.2 1267.71  5540.2 1269.17
#Mann=6,-1,0
  4785.7    0.05       0  4910.9    0.12       0  4985.5    0.07       0
  4989.5    0.12       0  5145.2    0.05       0  5477.6    0.12       0
Bank Sta=4985.5,4989.5
Exp/Cntr=0.3,0.1

Type RM Length L Ch R = 1,53000,500,500,500
BEGIN DESCRIPTION:
FLAG CREEK 105.0
END DESCRIPTION:
XS GIS Cut Line= 3
      2802580.69     10213178.11      2802988.75     10213194.83
      2803105.69     10212853.09
#Sta/Elev= 30
  4591.6 1255.39  4606.6 1254.50  4626.6 1254.71  4696.7 1251.30  4726.7 1250.57
  4796.8 1246.79  4833.8 1242.84  4838.8 1243.71  4896.8 1240.12  4966.9 1237.99
  4996.0 1236.09  5021.0 1235.30  5021.2 1234.80  5024.7 1234.80  5025.0 1235.30
  5063.9 1237.54  5107.5 1241.58  5118.1 1242.04  5126.4 1243.24  5131.7 1243.21
  5157.7 1246.37  5163.0 1246.28  5220.3 1252.25  5225.6 1252.01  5251.6 1255.21
  5256.9 1254.89  5282.9 1257.67  5288.2 1257.02  5305.9 1258.30  5361.2 1262.16
#Mann=4,-1,0
  4591.6    0.05       0  5021.0    0.05       0  5025.0    0.05       0
  5305.9    0.12       0
Bank Sta=5021,5025
Exp/Cntr=0.3,0.1

Type RM Length L Ch R = 1,52500,500,500,500
BEGIN DESCRIPTION:
FLAG CREEK 104.0
END DESCRIPTION:
XS GIS Cut Line= 3
      2803055.68     10213703.12      2803394.76     10213447.74
      2803205.70     10212953.14
#Sta/Elev= 30
  4575.5 1251.29  4682.7 1244.95  4743.4 1242.73  4753.5 1241.43  4811.8 1239.50
  4832.7 1237.75  4908.6 1234.17  4961.7 1232.67  4976.1 1231.11  4982.6 1231.70
  4988.8 1230.24  4997.1 1230.91  4999.7 1227.98  5008.9 1227.85  5009.1 1227.35
  5012.9 1227.85  5016.2 1228.93  5065.6 1233.72  5103.8 1235.39  5179.3 1240.60
  5186.9 1241.51  5320.1 1246.74  5368.9 1249.92  5374.9 1251.30  5405.0 1251.04
  5484.4 1255.52  5489.8 1254.91  5508.1 1257.11  5514.5 1256.48  5529.5 1257.21
#Mann=7,-1,0
  4575.5    0.05       0  4743.4    0.12       0  4908.6    0.05       0
  5008.9    0.05       0  5012.9    0.05       0  5103.8    0.12       0
  5179.3    0.05       0
Bank Sta=5008.9,5012.9
Exp/Cntr=0.3,0.1

Type RM Length L Ch R = 1,52000,500,500,500
BEGIN DESCRIPTION:
FLAG CREEK 103.0
END DESCRIPTION:
XS GIS Cut Line= 3
      2803205.69     10213753.11      2803887.16     10213382.14
      2804051.71     10212856.59
#Sta/Elev= 30
  4224.1 1248.79  4238.4 1248.64  4307.0 1248.32  4406.9 1243.64  4488.6 1236.02
  4548.4 1234.17  4564.6 1234.77  4599.8 1232.22  4709.8 1231.14  4861.4 1230.74
  4880.8 1230.89  4908.4 1227.91  4924.5 1228.62  4930.2 1226.79  4940.7 1227.43
  4946.4 1225.14  4962.5 1225.79  4968.2 1224.28  4984.4 1224.97  4988.1 1223.10
  4988.3 1222.60  4992.1 1223.10  5002.1 1223.11  5008.0 1224.75  5013.2 1223.22
  5040.5 1229.51  5103.8 1231.08  5315.8 1242.82  5459.3 1247.75  5550.7 1250.80
#Mann=8,-1,0
  4224.1    0.05       0  4238.4    0.12       0  4307.0    0.05       0
  4709.8    0.12       0  4861.4    0.05       0  4988.1    0.05       0
  4992.1    0.05       0  5459.3    0.12       0
Bank Sta=4988.1,4992.1
Exp/Cntr=0.3,0.1

Type RM Length L Ch R = 1,51500,500,500,500
BEGIN DESCRIPTION:
FLAG CREEK 102.0
END DESCRIPTION:
XS GIS Cut Line= 3
      2803405.64     10213703.11      2803887.10     10213734.77
      2804155.65     10213553.14
#Sta/Elev= 30
  4517.5 1242.88  4547.6 1239.94  4567.6 1238.85  4617.8 1237.66  4657.8 1233.90
  4744.6 1230.06  4841.1 1227.33  4843.2 1227.21  4888.3 1227.24  4948.5 1225.19
  4978.5 1223.44  4988.6 1222.30  4996.8 1220.26  5012.1 1219.14  5012.4 1218.64
  5015.9 1218.64  5016.1 1219.14  5050.1 1220.66  5058.6 1221.88  5065.1 1223.99
  5071.1 1223.87  5080.0 1224.98  5086.1 1224.66  5101.0 1225.84  5145.6 1226.71
  5202.9 1228.15  5238.8 1232.09  5244.8 1232.15  5251.8 1233.90  5324.2 1242.95
#Mann=6,-1,0
  4517.5    0.05       0  4841.1    0.12       0  4843.2    0.05       0
  5012.1    0.05       0  5016.1    0.05       0  5145.6    0.12       0
Bank Sta=5012.1,5016.1
Exp/Cntr=0.3,0.1

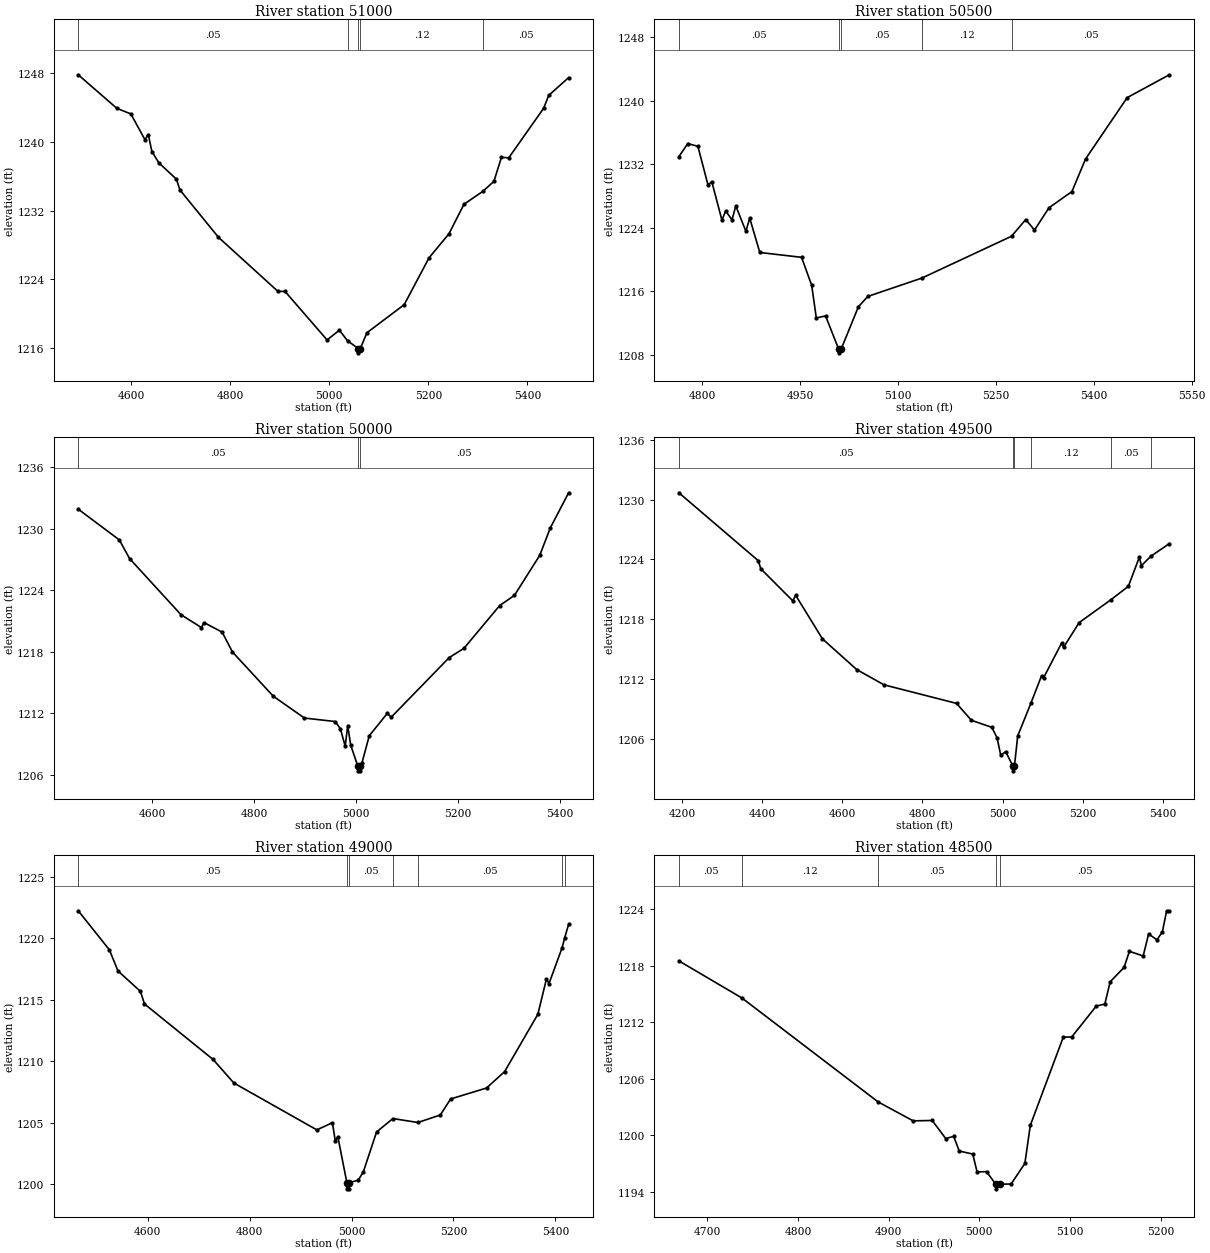
Type RM Length L Ch R = 1,51000,500,500,500
BEGIN DESCRIPTION:
FLAG CREEK 101.0
END DESCRIPTION:
XS GIS Cut Line= 3
      2803305.67     10213753.10      2803675.46     10214099.66
      2804155.69     10214153.11
#Sta/Elev= 30
  4493.2 1247.85  4571.1 1243.94  4599.4 1243.29  4627.8 1240.29  4634.6 1240.89
  4641.9 1238.90  4656.1 1237.58  4691.3 1235.69  4698.6 1234.42  4776.3 1228.91
  4896.4 1222.61  4910.6 1222.61  4995.6 1216.95  5020.4 1218.09  5036.8 1216.86
  5058.6 1215.95  5058.8 1215.45  5062.6 1215.95  5076.0 1217.79  5151.2 1221.06
  5201.5 1226.53  5241.7 1229.33  5271.9 1232.76  5310.1 1234.27  5332.3 1235.43
  5347.5 1238.22  5362.4 1238.18  5432.9 1243.96  5443.0 1245.45  5483.2 1247.52
#Mann=5,-1,0
  4493.2    0.05       0  5036.8    0.12       0  5058.6    0.05       0
  5062.6    0.12       0  5310.1    0.05       0
Bank Sta=5058.6,5062.6
Exp/Cntr=0.3,0.1

Type RM Length L Ch R = 1,50500,500,500,500
BEGIN DESCRIPTION:
FLAG CREEK 100.0
END DESCRIPTION:
XS GIS Cut Line= 3
      2803455.69     10214653.11      2803657.31     10214530.65
      2804055.66     10214203.13
#Sta/Elev= 30
  4764.1 1232.97  4777.7 1234.61  4793.2 1234.26  4808.7 1229.38  4814.5 1229.81
  4830.0 1224.96  4835.8 1226.10  4845.5 1224.99  4851.3 1226.75  4866.8 1223.54
  4872.6 1225.21  4888.1 1220.87  4952.1 1220.26  4967.6 1216.73  4974.7 1212.61
  4988.9 1212.87  5008.8 1208.71  5009.0 1208.21  5012.9 1208.71  5039.3 1214.04
  5053.7 1215.33  5136.4 1217.64  5273.9 1222.92  5295.7 1225.03  5309.1 1223.70
  5331.3 1226.51  5366.5 1228.56  5387.3 1232.66  5451.2 1240.41  5515.7 1243.29
#Mann=5,-1,0
  4764.1    0.05       0  5008.8    0.05       0  5012.9    0.05       0
  5136.4    0.12       0  5273.9    0.05       0
Bank Sta=5008.8,5012.9
Exp/Cntr=0.3,0.1

Type RM Length L Ch R = 1,50000,500,500,500
BEGIN DESCRIPTION:
FLAG CREEK 99.0
END DESCRIPTION:
XS GIS Cut Line= 3
      2803405.71     10214853.12      2803946.09     10214930.52
      2804205.66     10214603.14
#Sta/Elev= 30
  4454.1 1231.92  4534.9 1228.92  4555.0 1227.10  4656.1 1221.62  4696.2 1220.37
  4701.2 1220.86  4736.9 1219.92  4757.1 1217.99  4837.4 1213.67  4898.6 1211.54
  4959.2 1211.20  4969.3 1210.49  4978.7 1208.79  4983.7 1210.81  4989.5 1208.90
  5003.2 1206.89  5003.4 1206.39  5007.0 1206.39  5007.3 1206.89  5011.6 1207.15
  5026.0 1209.81  5061.3 1211.99  5069.3 1211.63  5183.1 1217.44  5212.0 1218.34
  5282.4 1222.52  5311.3 1223.51  5361.0 1227.41  5381.8 1230.09  5417.8 1233.52
#Mann=3,-1,0
  4454.1    0.05       0  5003.2    0.05       0  5007.3    0.05       0
Bank Sta=5003.2,5007.3
Exp/Cntr=0.3,0.1

Type RM Length L Ch R = 1,49500,500,500,500
BEGIN DESCRIPTION:
FLAG CREEK 98.0
END DESCRIPTION:
XS GIS Cut Line= 3
      2803405.66     10214953.10      2804098.78     10215367.41
      2804505.65     10215453.10
#Sta/Elev= 30
  4192.5 1230.68  4390.6 1223.87  4396.8 1223.06  4476.5 1219.85  4483.8 1220.40
  4550.5 1216.04  4636.1 1212.96  4704.2 1211.43  4885.1 1209.57  4922.0 1207.88
  4973.1 1207.17  4986.2 1206.12  4995.3 1204.38  5007.8 1204.73  5025.4 1203.31
  5025.6 1202.81  5029.6 1203.31  5037.7 1206.31  5070.5 1209.58  5097.2 1212.34
  5102.3 1212.14  5147.0 1215.60  5152.1 1215.19  5191.0 1217.67  5270.5 1219.97
  5313.6 1221.30  5341.1 1224.22  5346.2 1223.38  5370.5 1224.34  5415.8 1225.58
#Mann=6,-1,0
  4192.5    0.05       0  5025.4    0.05       0  5029.6    0.05       0
  5070.5    0.12       0  5270.5    0.05       0  5370.5    0.12       0
Bank Sta=5025.4,5029.6
Exp/Cntr=0.3,0.1

Type RM Length L Ch R = 1,49000,500,500,500
BEGIN DESCRIPTION:
FLAG CREEK 97.0
END DESCRIPTION:
XS GIS Cut Line= 3
      2803555.72     10215753.12      2804082.74     10215854.06
      2804505.69     10215803.11
#Sta/Elev= 30
  4463.4 1222.22  4524.5 1219.05  4541.4 1217.33  4585.5 1215.67  4593.4 1214.65
  4728.1 1210.14  4768.8 1208.23  4931.7 1204.42  4962.3 1205.00  4967.9 1203.54
  4973.0 1203.86  4990.7 1200.13  4991.0 1199.63  4994.7 1199.63  4995.0 1200.13
  5013.0 1200.33  5023.1 1201.02  5049.0 1204.25  5081.1 1205.34  5130.2 1205.02
  5174.2 1205.63  5194.3 1206.93  5264.8 1207.82  5300.3 1209.15  5365.6 1213.81
  5382.4 1216.67  5387.5 1216.31  5413.0 1219.19  5418.0 1219.98  5426.0 1221.12
#Mann=7,-1,0
  4463.4    0.05       0  4990.7    0.05       0  4995.0    0.05       0
  5081.1    0.12       0  5130.2    0.05       0  5413.0    0.12       0
  5418.0    0.05       0
Bank Sta=4990.7,4995
Exp/Cntr=0.3,0.1

Type RM Length L Ch R = 1,48500,500,500,500
BEGIN DESCRIPTION:
FLAG CREEK 96.0
END DESCRIPTION:
XS GIS Cut Line= 3
      2804205.67     10216403.13      2804393.50     10216130.10
      2804505.66     10215953.15
#Sta/Elev= 30
  4668.6 1218.53  4738.2 1214.58  4888.4 1203.53  4927.0 1201.52  4948.0 1201.56
  4962.9 1199.64  4971.7 1199.87  4977.8 1198.31  4992.7 1197.99  4997.5 1196.09
  5007.9 1196.12  5018.0 1194.79  5018.3 1194.29  5022.3 1194.79  5035.0 1194.80
  5050.2 1196.99  5056.2 1201.04  5092.6 1210.43  5101.9 1210.44  5129.0 1213.73
  5138.4 1213.94  5144.3 1216.31  5159.6 1217.83  5165.5 1219.55  5180.7 1219.05
  5186.7 1221.39  5196.0 1220.77  5201.9 1221.63  5206.6 1223.86  5209.5 1223.86
#Mann=5,-1,0
  4668.6    0.05       0  4738.2    0.12       0  4888.4    0.05       0
  5018.0    0.05       0  5022.3    0.05       0
Bank Sta=5018,5022.3
Exp/Cntr=0.3,0.1