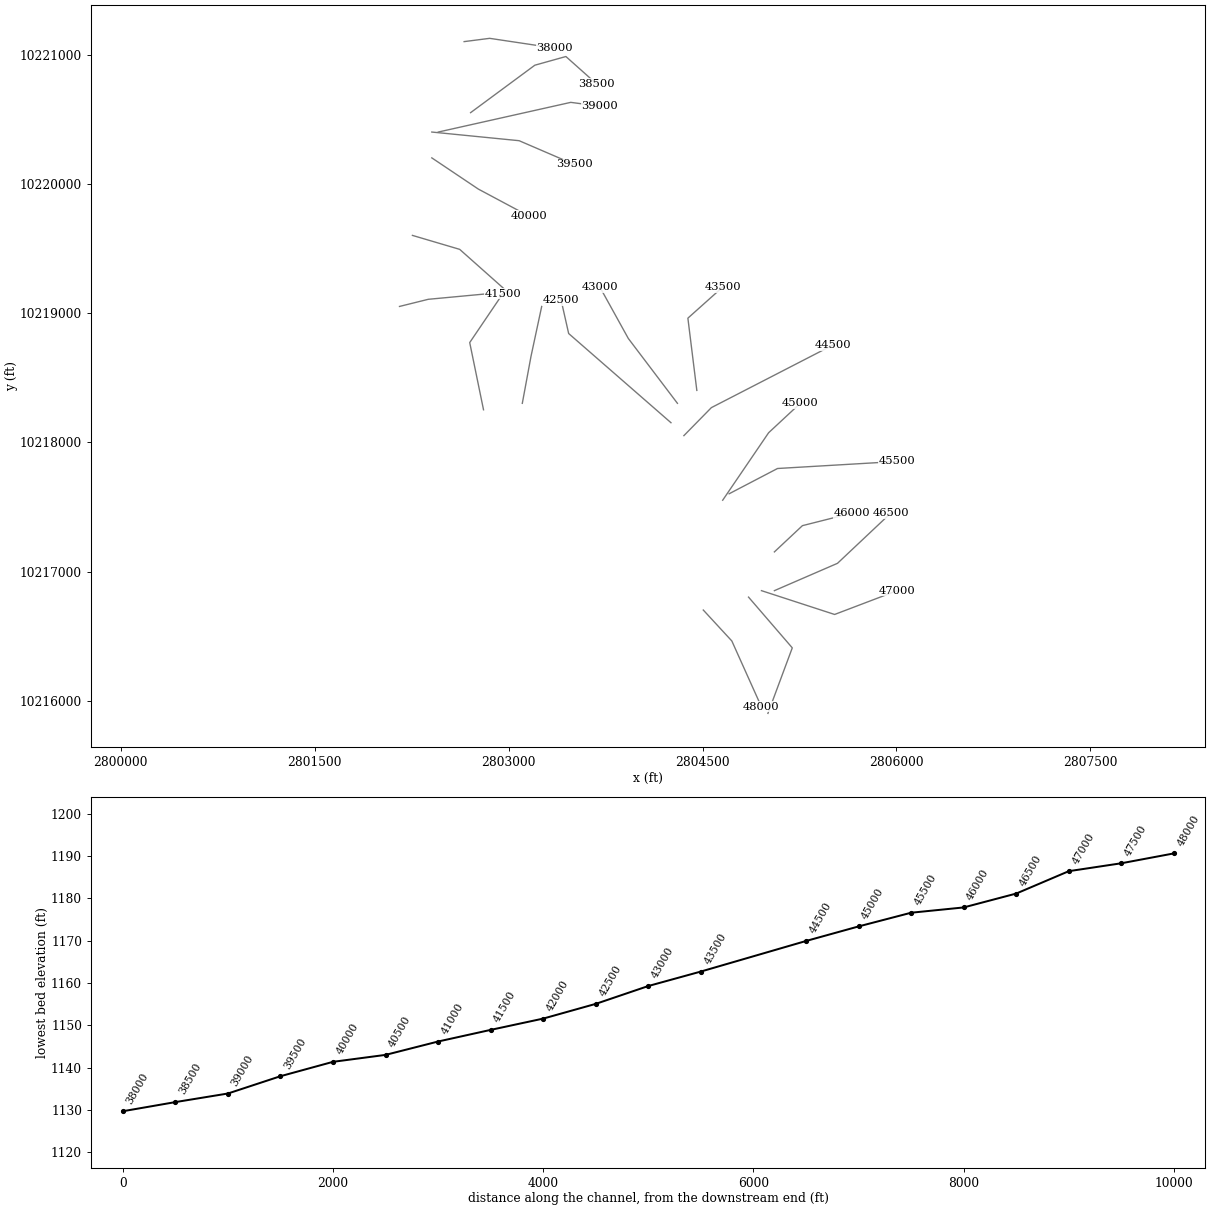
HEC-RAS study FLAG CREEK.prj: FLAG CREEK Base Level Engineering

--- FLAG CREEK.g01 (geometry) --- (continued)

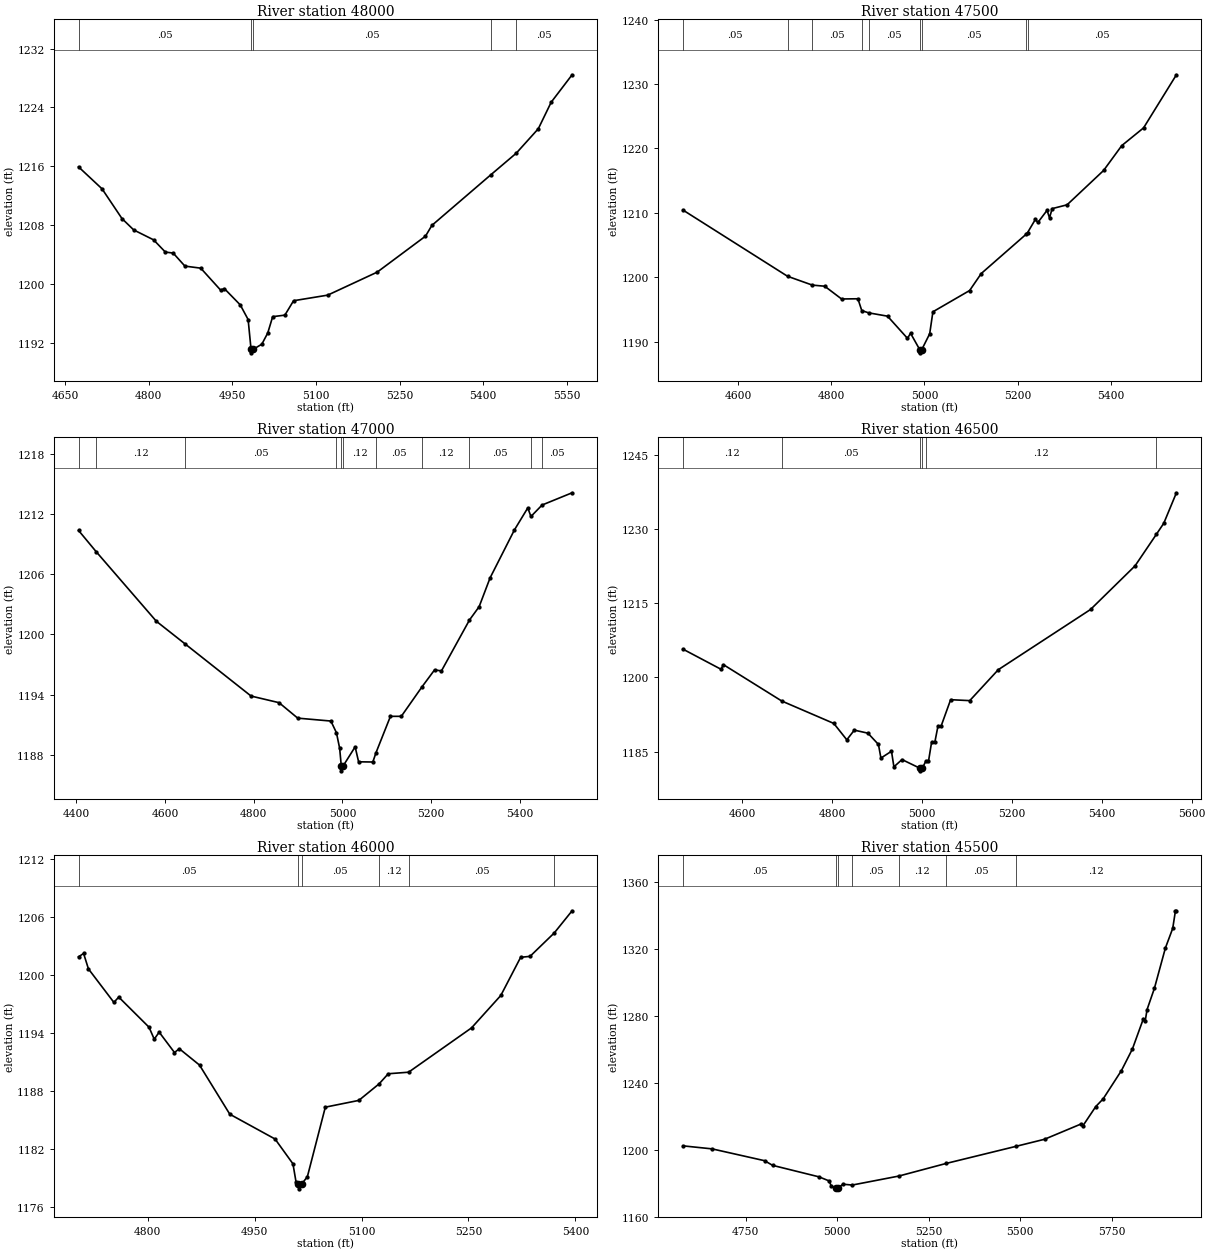
Type RM Length L Ch R = 1,48000,500,500,500
BEGIN DESCRIPTION:
FLAG CREEK 95.0
END DESCRIPTION:
XS GIS Cut Line= 3
      2804505.68     10216703.11      2804726.50     10216463.56
      2804955.67     10215953.14
#Sta/Elev= 30
  4674.2 1215.91  4716.4 1212.92  4752.2 1208.87  4773.2 1207.33  4808.9 1205.98
  4829.9 1204.32  4844.0 1204.18  4865.0 1202.41  4893.4 1202.13  4929.1 1199.14
  4935.9 1199.34  4964.3 1197.13  4978.4 1195.14  4983.6 1191.11  4983.9 1190.61
  4988.0 1191.11  5003.0 1191.79  5013.6 1193.31  5022.4 1195.53  5044.3 1195.74
  5059.9 1197.70  5121.1 1198.46  5209.9 1201.59  5296.5 1206.48  5308.0 1207.95
  5413.5 1214.82  5459.3 1217.77  5498.9 1221.10  5522.0 1224.71  5559.5 1228.44
#Mann=5,-1,0
  4674.2    0.05       0  4983.6    0.05       0  4988.0    0.05       0
  5413.5    0.12       0  5459.3    0.05       0
Bank Sta=4983.6,4988
Exp/Cntr=0.3,0.1

Type RM Length L Ch R = 1,47500,500,500,500
BEGIN DESCRIPTION:
FLAG CREEK 94.0
END DESCRIPTION:
XS GIS Cut Line= 3
      2804855.67     10216803.13      2805194.07     10216410.29
      2805005.70     10215903.14
#Sta/Elev= 30
  4481.5 1210.45  4706.3 1200.16  4759.5 1198.79  4786.0 1198.62  4822.2 1196.64
  4857.3 1196.67  4865.6 1194.84  4880.1 1194.49  4920.9 1193.97  4963.7 1190.53
  4970.3 1191.32  4990.0 1188.78  4990.3 1188.28  4994.4 1188.78  5011.4 1191.24
  5018.3 1194.65  5097.1 1197.95  5122.1 1200.59  5218.8 1206.71  5221.6 1206.95
  5238.2 1208.98  5243.6 1208.51  5263.3 1210.39  5268.6 1209.23  5274.3 1210.66
  5306.3 1211.25  5384.7 1216.58  5423.7 1220.44  5470.5 1223.19  5541.0 1231.43
#Mann=9,-1,0
  4481.5    0.05       0  4706.3    0.12       0  4759.5    0.05       0
  4865.6    0.12       0  4880.1    0.05       0  4990.0    0.05       0
  4994.4    0.05       0  5218.8    0.12       0  5221.6    0.05       0
Bank Sta=4990,4994.4
Exp/Cntr=0.3,0.1

Type RM Length L Ch R = 1,47000,500,500,500
BEGIN DESCRIPTION:
FLAG CREEK 93.0
END DESCRIPTION:
XS GIS Cut Line= 3
      2804955.70     10216853.11      2805521.54     10216668.80
      2806005.64     10216853.10
#Sta/Elev= 30
  4404.9 1210.36  4444.5 1208.25  4580.4 1201.31  4645.9 1199.03  4794.0 1193.86
  4857.1 1193.20  4899.2 1191.66  4974.0 1191.37  4986.5 1190.21  4993.8 1188.65
  4997.4 1186.91  4997.7 1186.41  5001.8 1186.91  5028.7 1188.80  5036.5 1187.31
  5068.6 1187.29  5075.6 1188.20  5108.3 1191.84  5132.8 1191.84  5179.5 1194.78
  5207.7 1196.46  5223.4 1196.37  5286.6 1201.44  5308.3 1202.76  5333.1 1205.64
  5387.9 1210.41  5418.0 1212.60  5425.2 1211.75  5450.3 1212.89  5518.0 1214.11
#Mann=11,-1,0
  4404.9    0.05       0  4444.5    0.12       0  4645.9    0.05       0
  4986.5    0.12       0  4997.4    0.07       0  5001.8    0.12       0
  5075.6    0.05       0  5179.5    0.12       0  5286.6    0.05       0
  5425.2    0.12       0  5450.3    0.05       0
Bank Sta=4997.4,5001.8
Exp/Cntr=0.3,0.1

Type RM Length L Ch R = 1,46500,500,500,500
BEGIN DESCRIPTION:
FLAG CREEK 92.0
END DESCRIPTION:
XS GIS Cut Line= 3
      2805055.68     10216853.11      2805543.78     10217064.73
      2805955.66     10217453.09
#Sta/Elev= 30
  4468.0 1205.73  4552.9 1201.65  4558.3 1202.58  4688.1 1195.23  4803.9 1190.70
  4832.8 1187.39  4849.5 1189.35  4879.8 1188.73  4903.2 1186.45  4908.7 1183.70
  4932.2 1185.08  4937.6 1181.93  4955.6 1183.40  4996.1 1181.62  4996.4 1181.12
  5000.6 1181.62  5008.3 1183.03  5014.5 1183.04  5021.4 1186.89  5028.7 1186.93
  5035.5 1190.11  5042.8 1190.21  5063.8 1195.50  5106.3 1195.31  5169.8 1201.56
  5375.0 1213.73  5474.1 1222.55  5521.8 1228.96  5538.0 1231.16  5566.1 1237.32
#Mann=6,-1,0
  4468.0    0.12       0  4688.1    0.05       0  4996.1    0.03       0
  5000.6    0.05       0  5008.3    0.12       0  5521.8    0.05       0
Bank Sta=4996.1,5000.6
Exp/Cntr=0.3,0.1

Type RM Length L Ch R = 1,46000,500,500,500
BEGIN DESCRIPTION:
FLAG CREEK 91.0
END DESCRIPTION:
XS GIS Cut Line= 3
      2805055.69     10217153.11      2805272.37     10217356.23
      2805655.72     10217453.12
#Sta/Elev= 30
  4703.0 1201.87  4710.1 1202.22  4716.9 1200.62  4752.6 1197.15  4759.4 1197.70
  4801.9 1194.58  4809.2 1193.34  4816.1 1194.07  4837.6 1191.96  4844.4 1192.35
  4872.7 1190.66  4915.2 1185.57  4978.7 1183.00  5003.8 1180.43  5008.1 1178.56
  5011.5 1178.34  5011.8 1177.84  5016.0 1178.34  5024.0 1179.09  5049.2 1186.30
  5096.2 1187.00  5124.6 1188.71  5137.5 1189.76  5166.0 1189.92  5254.3 1194.51
  5295.4 1197.87  5323.2 1201.82  5336.4 1201.92  5370.3 1204.34  5395.4 1206.64
#Mann=6,-1,0
  4703.0    0.05       0  5011.5    0.05       0  5016.0    0.05       0
  5124.6    0.12       0  5166.0    0.05       0  5370.3    0.12       0
Bank Sta=5011.5,5016
Exp/Cntr=0.3,0.1

Type RM Length L Ch R = 1,45500,500,500,500
BEGIN DESCRIPTION:
FLAG CREEK 90.0
END DESCRIPTION:
XS GIS Cut Line= 3
      2804705.66     10217603.10      2805079.83     10217798.67
      2806005.73     10217853.11
#Sta/Elev= 30
  4577.8 1202.30  4657.9 1200.48  4801.2 1193.42  4823.3 1190.63  4950.1 1183.76
  4977.8 1181.33  4984.0 1178.16  4997.1 1177.09  4997.4 1176.59  5001.6 1177.09
  5015.9 1179.34  5041.1 1178.86  5168.2 1184.22  5297.6 1191.76  5488.9 1202.00
  5566.8 1206.22  5667.0 1215.39  5672.0 1214.35  5707.1 1225.82  5727.1 1230.36
  5777.2 1247.31  5807.2 1260.22  5837.3 1278.37  5842.3 1277.11  5847.3 1283.81
  5867.3 1296.46  5897.4 1320.60  5917.4 1332.31  5924.9 1342.84  5927.5 1342.84
#Mann=7,-1,0
  4577.8    0.05       0  4997.1    0.07       0  5001.6    0.05       0
  5041.1    0.05       0  5168.2    0.12       0  5297.6    0.05       0
  5488.9    0.12       0
Bank Sta=4997.1,5001.6
Exp/Cntr=0.3,0.1

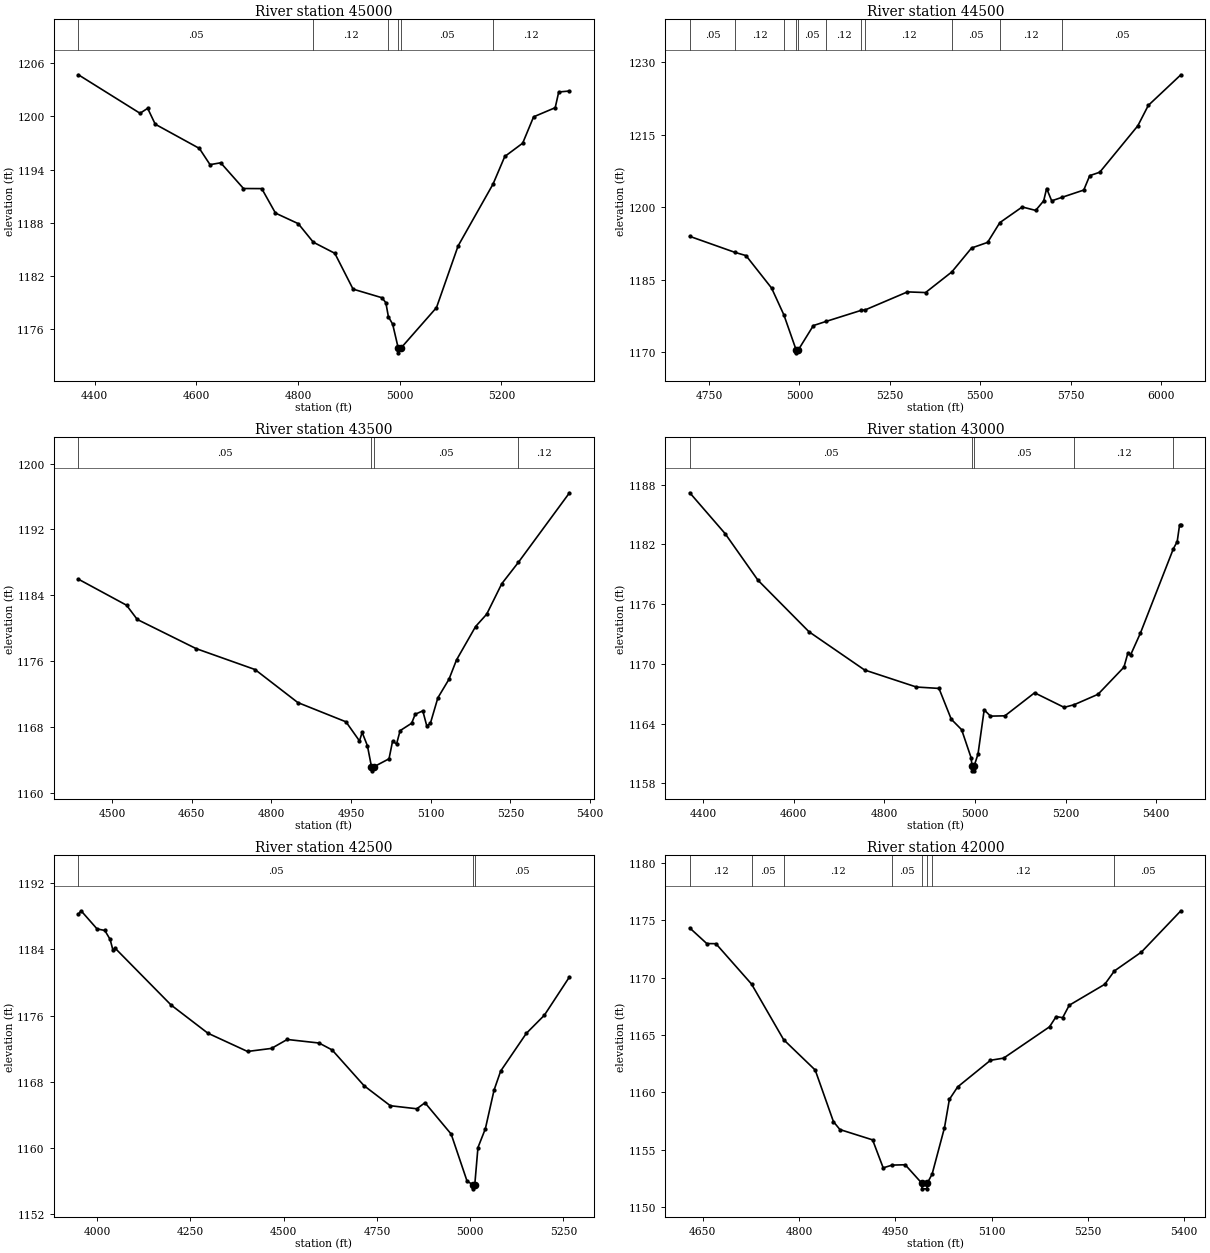
Type RM Length L Ch R = 1,45000,500,500,500
BEGIN DESCRIPTION:
FLAG CREEK 89.0
END DESCRIPTION:
XS GIS Cut Line= 3
      2804655.70     10217553.14      2805011.15     10218075.59
      2805255.68     10218303.10
#Sta/Elev= 30
  4368.1 1204.69  4489.3 1200.35  4504.3 1200.91  4519.2 1199.12  4606.0 1196.39
  4627.0 1194.56  4648.0 1194.77  4692.8 1191.87  4728.7 1191.86  4755.7 1189.10
  4800.5 1187.91  4830.1 1185.82  4872.4 1184.57  4908.3 1180.53  4965.2 1179.56
  4972.8 1179.00  4977.8 1177.42  4986.2 1176.58  4997.3 1173.85  4997.6 1173.35
  5001.9 1173.85  5072.4 1178.45  5114.9 1185.40  5183.6 1192.37  5206.7 1195.48
  5241.9 1196.98  5263.4 1199.95  5305.9 1200.98  5312.8 1202.75  5334.0 1202.86
#Mann=6,-1,0
  4368.1    0.05       0  4830.1    0.12       0  4977.8    0.05       0
  4997.3    0.05       0  5001.9    0.05       0  5183.6    0.12       0
Bank Sta=4997.3,5001.9
Exp/Cntr=0.3,0.1

Type RM Length L Ch R = 1,44500,1000,1000,1000
BEGIN DESCRIPTION:
FLAG CREEK 88.0
END DESCRIPTION:
XS GIS Cut Line= 3
      2804355.67     10218053.10      2804568.06     10218269.76
      2805505.71     10218753.12
#Sta/Elev= 30
  4696.6 1194.01  4821.8 1190.69  4852.1 1190.03  4922.9 1183.31  4956.9 1177.76
  4991.3 1170.41  4991.6 1169.91  4995.9 1170.41  5038.4 1175.55  5074.0 1176.42
  5169.8 1178.68  5182.6 1178.82  5298.7 1182.52  5348.7 1182.38  5421.4 1186.65
  5476.0 1191.60  5520.3 1192.76  5554.2 1196.85  5616.1 1200.09  5653.3 1199.38
  5675.5 1201.36  5683.6 1203.91  5697.6 1201.36  5726.7 1202.10  5786.3 1203.59
  5802.8 1206.57  5830.6 1207.28  5935.8 1216.88  5964.9 1221.11  6054.9 1227.44
#Mann=11,-1,0
  4696.6    0.05       0  4821.8    0.12       0  4956.9    0.05       0
  4991.3    0.03       0  4995.9    0.05       0  5074.0    0.12       0
  5169.8    0.05       0  5182.6    0.12       0  5421.4    0.05       0
  5554.2    0.12       0  5726.7    0.05       0
Bank Sta=4991.3,4995.9
Exp/Cntr=0.3,0.1

Type RM Length L Ch R = 1,43500,500,500,500
BEGIN DESCRIPTION:
FLAG CREEK 87.0
END DESCRIPTION:
XS GIS Cut Line= 3
      2804455.68     10218403.15      2804386.49     10218962.39
      2804655.66     10219203.09
#Sta/Elev= 30
  4436.5 1185.96  4527.1 1182.80  4547.3 1181.07  4658.1 1177.53  4769.0 1174.99
  4849.6 1170.98  4940.3 1168.64  4965.7 1166.32  4970.7 1167.36  4980.6 1165.74
  4988.3 1163.19  4988.7 1162.69  4993.0 1163.19  5021.3 1164.15  5028.0 1166.29
  5035.5 1165.95  5042.2 1167.57  5063.9 1168.47  5070.6 1169.56  5084.9 1169.97
  5092.4 1168.14  5099.1 1168.44  5113.3 1171.56  5134.2 1173.81  5148.4 1176.16
  5184.3 1180.21  5205.2 1181.71  5233.6 1185.41  5264.7 1187.99  5361.1 1196.45
#Mann=4,-1,0
  4436.5    0.05       0  4988.3    0.05       0  4993.0    0.05       0
  5264.7    0.12       0
Bank Sta=4988.3,4993
Exp/Cntr=0.3,0.1

Type RM Length L Ch R = 1,43000,500,500,500
BEGIN DESCRIPTION:
FLAG CREEK 86.0
END DESCRIPTION:
XS GIS Cut Line= 3
      2804305.69     10218303.10      2803925.64     10218805.31
      2803705.67     10219203.14
#Sta/Elev= 30
  4370.2 1187.17  4448.3 1183.07  4520.7 1178.40  4633.6 1173.22  4756.2 1169.39
  4870.6 1167.68  4920.5 1167.54  4947.6 1164.45  4970.5 1163.40  4991.3 1160.60
  4993.5 1159.77  4993.8 1159.27  4997.8 1159.27  4998.2 1159.77  5006.7 1160.96
  5020.3 1165.39  5034.2 1164.76  5066.1 1164.79  5131.6 1167.10  5196.8 1165.64
  5218.7 1165.90  5271.7 1166.95  5328.9 1169.67  5337.7 1171.10  5343.5 1170.89
  5365.2 1173.08  5438.1 1181.56  5446.5 1182.27  5451.7 1183.92  5454.6 1183.92
#Mann=5,-1,0
  4370.2    0.05       0  4993.5    0.05       0  4998.2    0.05       0
  5218.7    0.12       0  5438.1    0.05       0
Bank Sta=4993.5,4998.2
Exp/Cntr=0.3,0.1

Type RM Length L Ch R = 1,42500,500,500,500
BEGIN DESCRIPTION:
FLAG CREEK 85.0
END DESCRIPTION:
XS GIS Cut Line= 3
      2804255.72     10218153.08      2803464.24     10218843.51
      2803405.69     10219103.09
#Sta/Elev= 30
  3949.7 1188.25  3956.9 1188.67  3999.6 1186.48  4020.5 1186.29  4034.7 1185.21
  4042.3 1183.90  4048.9 1184.11  4198.0 1177.28  4296.7 1173.87  4403.0 1171.66
  4467.3 1172.03  4509.4 1173.11  4594.8 1172.68  4629.9 1171.84  4715.4 1167.52
  4785.8 1165.10  4856.8 1164.73  4878.7 1165.46  4948.9 1161.67  4991.6 1155.97
  5007.4 1155.55  5007.8 1155.05  5012.2 1155.55  5020.7 1160.04  5040.6 1162.32
  5063.9 1166.99  5081.6 1169.29  5150.4 1173.85  5198.7 1176.04  5266.1 1180.68
#Mann=3,-1,0
  3949.7    0.05       0  5007.4    0.05       0  5012.2    0.05       0
Bank Sta=5007.4,5012.2
Exp/Cntr=0.3,0.1

Type RM Length L Ch R = 1,42000,500,500,500
BEGIN DESCRIPTION:
FLAG CREEK 84.0
END DESCRIPTION:
XS GIS Cut Line= 3
      2803105.68     10218303.06      2803173.02     10218667.19
      2803255.69     10219053.13
#Sta/Elev= 30
  4629.7 1174.32  4656.2 1172.96  4670.4 1172.95  4725.9 1169.43  4775.9 1164.58
  4825.1 1161.93  4853.5 1157.43  4863.6 1156.74  4914.5 1155.84  4931.0 1153.40
  4944.9 1153.64  4965.3 1153.67  4991.0 1152.07  4991.5 1151.57  4999.2 1151.57
  4999.7 1152.07  5007.2 1152.85  5026.5 1156.91  5034.1 1159.37  5047.0 1160.46
  5098.1 1162.78  5118.6 1162.97  5190.1 1165.70  5200.4 1166.59  5210.6 1166.50
  5220.8 1167.58  5276.2 1169.41  5291.1 1170.57  5333.3 1172.22  5394.7 1175.82
#Mann=8,-1,0
  4629.7    0.12       0  4725.9    0.05       0  4775.9    0.12       0
  4944.9    0.05       0  4991.0    0.03       0  4999.7    0.05       0
  5007.2    0.12       0  5291.1    0.05       0
Bank Sta=4991,4999.7
Exp/Cntr=0.3,0.1

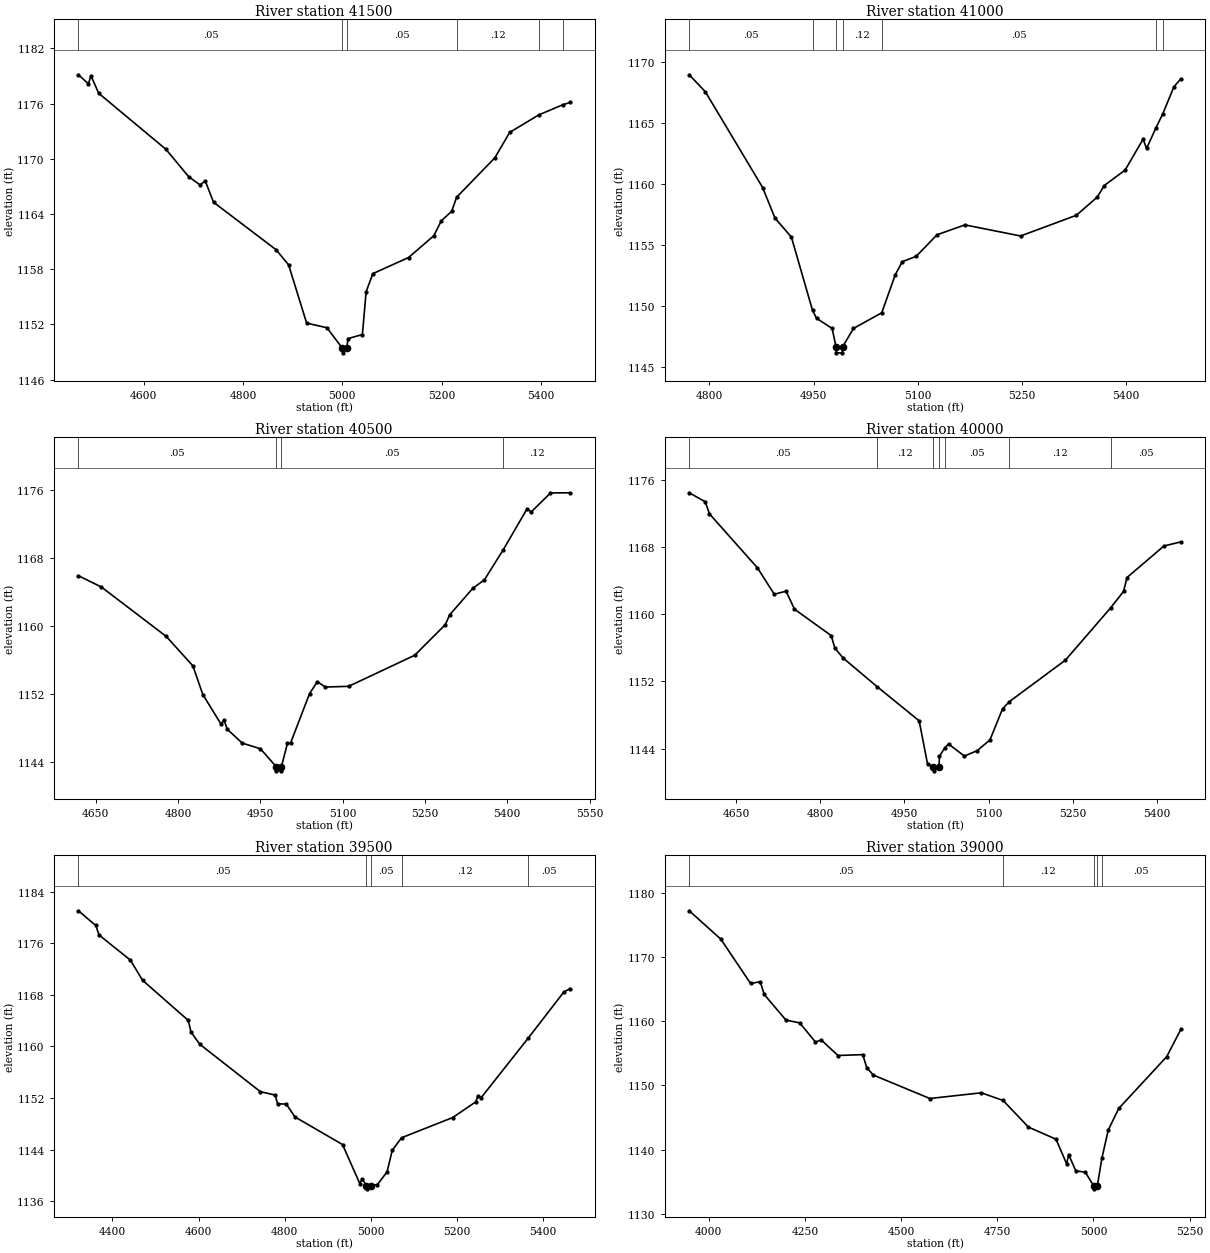
Type RM Length L Ch R = 1,41500,500,500,500
BEGIN DESCRIPTION:
FLAG CREEK 83.0
END DESCRIPTION:
XS GIS Cut Line= 3
      2802805.68     10218253.13      2802698.85     10218773.47
      2802955.71     10219153.15
#Sta/Elev= 30
  4468.8 1179.13  4488.9 1178.15  4494.0 1179.03  4509.6 1177.12  4645.1 1171.02
  4690.4 1168.07  4713.8 1167.15  4724.0 1167.60  4740.8 1165.27  4866.9 1160.10
  4891.9 1158.46  4928.2 1152.13  4969.0 1151.63  5000.1 1149.40  5000.6 1148.90
  5008.8 1149.40  5011.6 1150.45  5040.4 1150.89  5047.9 1155.53  5061.4 1157.51
  5133.3 1159.26  5184.2 1161.63  5199.2 1163.25  5220.2 1164.29  5230.0 1165.81
  5307.0 1170.10  5337.0 1172.87  5395.6 1174.77  5444.3 1175.88  5458.4 1176.12
#Mann=6,-1,0
  4468.8    0.05       0  5000.1    0.05       0  5008.8    0.05       0
  5230.0    0.12       0  5395.6    0.05       0  5444.3    0.12       0
Bank Sta=5000.1,5008.8
Exp/Cntr=0.3,0.1

Type RM Length L Ch R = 1,41000,500,500,500
BEGIN DESCRIPTION:
FLAG CREEK 82.0
END DESCRIPTION:
XS GIS Cut Line= 3
      2802155.70     10219053.12      2802378.14     10219108.36
      2802855.65     10219153.11
#Sta/Elev= 30
  4770.8 1168.97  4794.0 1167.58  4876.7 1159.71  4894.4 1157.21  4918.1 1155.65
  4948.6 1149.63  4954.3 1148.99  4976.9 1148.15  4982.4 1146.65  4982.9 1146.15
  4991.5 1146.15  4992.0 1146.65  5007.6 1148.15  5048.4 1149.44  5067.8 1152.55
  5077.9 1153.63  5098.0 1154.07  5128.1 1155.84  5168.3 1156.65  5248.6 1155.74
  5329.0 1157.44  5359.1 1158.93  5369.2 1159.88  5399.3 1161.15  5425.2 1163.69
  5430.2 1162.92  5443.5 1164.59  5453.6 1165.77  5469.6 1167.98  5479.6 1168.64
#Mann=7,-1,0
  4770.8    0.05       0  4948.6    0.12       0  4982.4    0.07       0
  4992.0    0.12       0  5048.4    0.05       0  5443.5    0.12       0
  5453.6    0.05       0
Bank Sta=4982.4,4992
Exp/Cntr=0.3,0.1

Type RM Length L Ch R = 1,40500,500,500,500
BEGIN DESCRIPTION:
FLAG CREEK 81.0
END DESCRIPTION:
XS GIS Cut Line= 3
      2802255.71     10219603.10      2802621.27     10219495.02
      2803005.71     10219153.09
#Sta/Elev= 30
  4618.8 1165.92  4660.5 1164.60  4778.9 1158.78  4827.3 1155.33  4845.5 1151.95
  4878.8 1148.46  4884.0 1148.98  4889.9 1147.88  4917.3 1146.25  4950.5 1145.58
  4978.9 1143.49  4979.4 1142.99  4988.2 1142.99  4988.7 1143.49  4999.7 1146.24
  5005.2 1146.24  5039.9 1152.06  5054.1 1153.48  5068.4 1152.84  5111.0 1152.92
  5231.4 1156.57  5287.4 1160.18  5295.0 1161.31  5337.6 1164.46  5358.5 1165.44
  5392.8 1168.97  5436.3 1173.80  5443.8 1173.42  5478.9 1175.65  5514.5 1175.67
#Mann=4,-1,0
  4618.8    0.05       0  4978.9    0.05       0  4988.7    0.05       0
  5392.8    0.12       0
Bank Sta=4978.9,4988.7
Exp/Cntr=0.3,0.1

Type RM Length L Ch R = 1,40000,500,500,500
BEGIN DESCRIPTION:
FLAG CREEK 80.0
END DESCRIPTION:
XS GIS Cut Line= 3
      2802405.71     10220203.09      2802765.50     10219961.64
      2803155.67     10219753.12
#Sta/Elev= 30
  4566.7 1174.43  4595.2 1173.36  4602.8 1171.92  4688.2 1165.50  4718.2 1162.36
  4739.2 1162.72  4754.2 1160.58  4819.6 1157.44  4826.2 1155.93  4841.2 1154.75
  4901.1 1151.38  4976.3 1147.30  4991.3 1142.12  5001.8 1141.85  5002.3 1141.35
  5011.6 1141.85  5012.4 1143.08  5022.1 1144.10  5028.6 1144.54  5056.9 1143.11
  5079.6 1143.75  5102.3 1145.02  5124.9 1148.74  5136.7 1149.57  5236.8 1154.52
  5317.6 1160.76  5340.4 1162.70  5346.5 1164.35  5412.3 1168.10  5442.4 1168.59
#Mann=7,-1,0
  4566.7    0.05       0  4901.1    0.12       0  5001.8    0.07       0
  5011.6    0.12       0  5022.1    0.05       0  5136.7    0.12       0
  5317.6    0.05       0
Bank Sta=5001.8,5011.6
Exp/Cntr=0.3,0.1

Type RM Length L Ch R = 1,39500,500,500,500
BEGIN DESCRIPTION:
FLAG CREEK 79.0
END DESCRIPTION:
XS GIS Cut Line= 3
      2802405.64     10220403.12      2803081.13     10220336.13
      2803505.66     10220153.12
#Sta/Elev= 30
  4321.2 1181.02  4361.4 1178.74  4369.2 1177.26  4441.8 1173.38  4470.1 1170.25
  4576.0 1164.05  4582.5 1162.24  4602.6 1160.36  4743.3 1153.01  4777.9 1152.47
  4783.5 1151.12  4803.6 1151.08  4823.7 1149.09  4934.2 1144.81  4974.4 1138.75
  4979.7 1139.49  4989.6 1138.45  4990.1 1137.95  4999.5 1138.45  5015.3 1138.62
  5037.6 1140.58  5049.7 1143.93  5071.2 1145.86  5190.1 1149.00  5243.4 1151.42
  5248.8 1152.39  5255.4 1152.02  5365.5 1161.32  5447.8 1168.43  5462.3 1168.97
#Mann=5,-1,0
  4321.2    0.05       0  4989.6    0.05       0  4999.5    0.05       0
  5071.2    0.12       0  5365.5    0.05       0
Bank Sta=4989.6,4999.5
Exp/Cntr=0.3,0.1

Type RM Length L Ch R = 1,39000,500,500,500
BEGIN DESCRIPTION:
FLAG CREEK 78.0
END DESCRIPTION:
XS GIS Cut Line= 3
      2802455.65     10220403.10      2803480.61     10220632.89
      2803705.65     10220603.12
#Sta/Elev= 30
  3949.6 1177.26  4031.6 1172.84  4109.1 1165.91  4134.1 1166.19  4144.3 1164.21
  4200.9 1160.20  4236.6 1159.76  4277.6 1156.78  4292.7 1157.09  4336.1 1154.67
  4400.6 1154.81  4410.8 1152.78  4427.9 1151.62  4574.8 1147.96  4708.5 1148.85
  4765.2 1147.65  4831.0 1143.50  4902.7 1141.60  4930.4 1137.74  4935.5 1139.21
  4954.0 1136.68  4978.9 1136.45  5000.2 1134.36  5000.7 1133.86  5010.1 1134.36
  5021.8 1138.62  5038.4 1143.04  5065.6 1146.40  5190.3 1154.49  5227.0 1158.74
#Mann=5,-1,0
  3949.6    0.05       0  4765.2    0.12       0  5000.2    0.07       0
  5010.1    0.12       0  5021.8    0.05       0
Bank Sta=5000.2,5010.1
Exp/Cntr=0.3,0.1

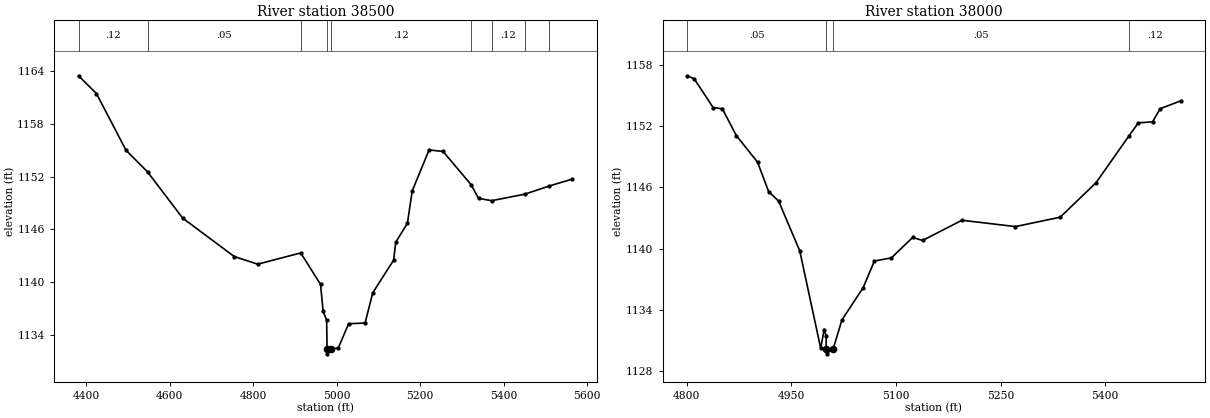
Type RM Length L Ch R = 1,38500,500,500,500
BEGIN DESCRIPTION:
FLAG CREEK 77.0
END DESCRIPTION:
XS GIS Cut Line= 4
      2802705.69     10220553.12      2803202.70     10220920.57
      2803442.82     10220987.70      2803677.20     10220778.62
#Sta/Elev= 30
  4381.9 1163.49  4424.7 1161.47  4495.6 1155.01  4547.2 1152.54  4631.3 1147.28
  4754.6 1142.91  4810.9 1142.04  4913.9 1143.32  4961.2 1139.74  4967.4 1136.70
  4975.8 1135.64  4977.0 1132.33  4977.5 1131.83  4987.0 1132.33  5004.1 1132.54
  5028.5 1135.26  5067.9 1135.34  5086.2 1138.78  5136.2 1142.50  5141.4 1144.55
  5169.2 1146.70  5180.7 1150.38  5221.1 1155.05  5254.6 1154.87  5321.8 1151.08
  5339.5 1149.53  5371.0 1149.27  5450.2 1150.01  5508.7 1150.94  5563.4 1151.72
#Mann=9,-1,0
  4381.9    0.12       0  4547.2    0.05       0  4913.9    0.12       0
  4977.0    0.07       0  4987.0    0.12       0  5321.8    0.05       0
  5371.0    0.12       0  5450.2    0.05       0  5508.7    0.12       0
Bank Sta=4977,4987
Exp/Cntr=0.3,0.1

Type RM Length L Ch R = 1,38000,500,500,500
BEGIN DESCRIPTION:
FLAG CREEK 76.0
END DESCRIPTION:
XS GIS Cut Line= 3
      2802655.72     10221103.12      2802853.20     10221128.49
      2803355.68     10221053.11
#Sta/Elev= 30
  4800.9 1156.96  4810.9 1156.67  4838.1 1153.84  4851.3 1153.72  4871.4 1151.08
  4901.7 1148.49  4917.7 1145.58  4931.9 1144.66  4962.2 1139.78  4992.2 1130.22
  4997.2 1132.05  5000.0 1131.44  5000.1 1130.17  5000.6 1129.67  5010.1 1130.17
  5022.7 1133.01  5053.1 1136.17  5069.1 1138.78  5093.5 1139.09  5123.9 1141.09
  5138.2 1140.80  5194.6 1142.78  5271.3 1142.16  5335.4 1143.08  5386.8 1146.47
  5433.9 1151.06  5447.4 1152.34  5467.7 1152.44  5478.6 1153.73  5508.1 1154.50
#Mann=4,-1,0
  4800.9    0.05       0  5000.1    0.05       0  5010.1    0.05       0
  5433.9    0.12       0
Bank Sta=5000.1,5010.1
Exp/Cntr=0.3,0.1