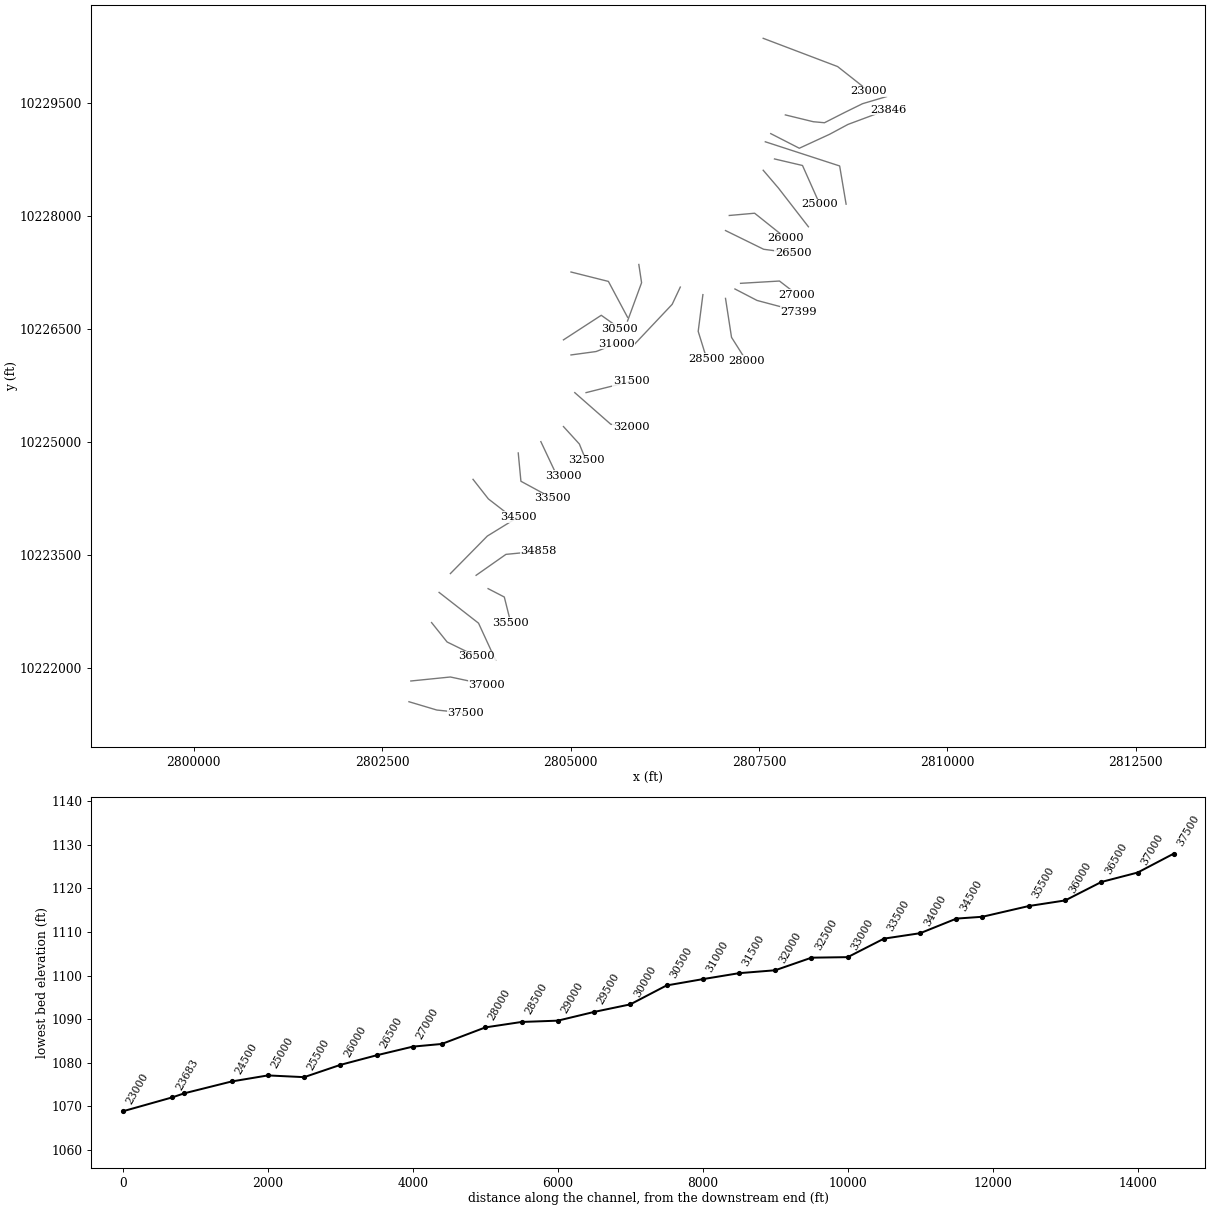
HEC-RAS study FLAG CREEK.prj: FLAG CREEK Base Level Engineering

--- FLAG CREEK.g01 (geometry) --- (continued)

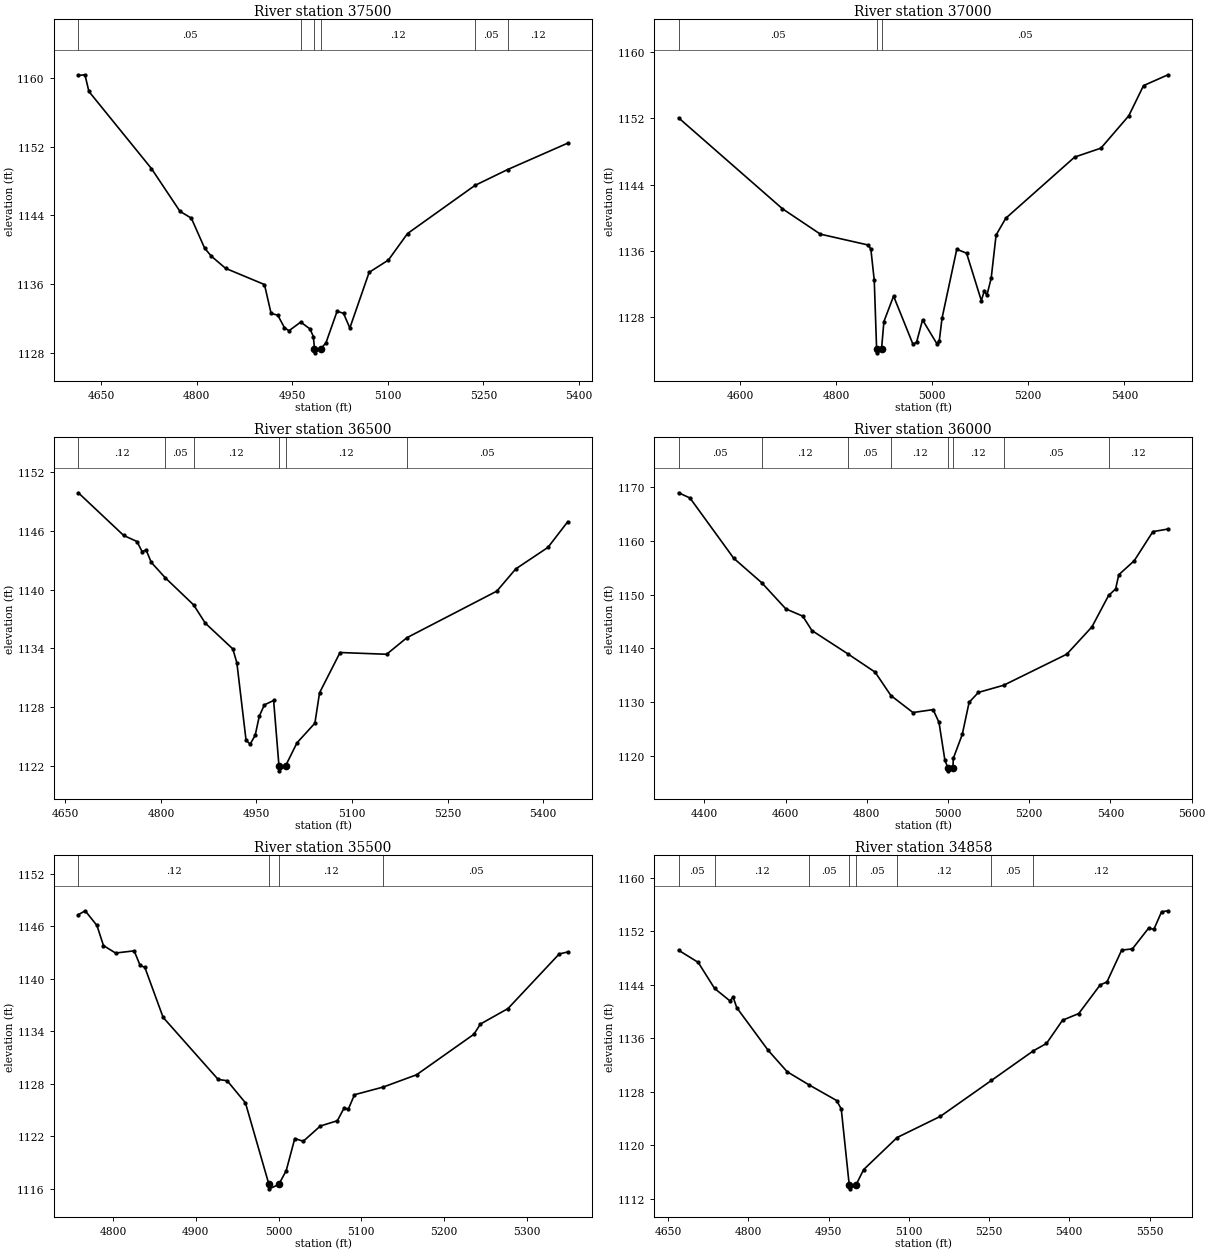
Type RM Length L Ch R = 1,37500,500,500,500
BEGIN DESCRIPTION:
FLAG CREEK 75.0
END DESCRIPTION:
XS GIS Cut Line= 3
      2802855.68     10221553.11      2803225.58     10221442.80
      2803605.71     10221403.11
#Sta/Elev= 30
  4614.0 1160.30  4624.4 1160.38  4630.6 1158.44  4728.8 1149.46  4773.6 1144.48
  4791.4 1143.69  4812.3 1140.19  4822.7 1139.27  4845.1 1137.85  4906.2 1135.96
  4916.6 1132.60  4927.1 1132.39  4937.5 1130.95  4944.6 1130.58  4963.1 1131.59
  4977.7 1130.79  4982.9 1129.91  4984.7 1128.51  4985.2 1128.01  4994.7 1128.51
  5002.6 1129.15  5020.2 1132.85  5030.3 1132.61  5040.2 1130.90  5070.5 1137.38
  5100.7 1138.81  5130.8 1141.90  5236.6 1147.50  5287.7 1149.34  5382.2 1152.42
#Mann=6,-1,0
  4614.0    0.05       0  4963.1    0.12       0  4984.7    0.07       0
  4994.7    0.12       0  5236.6    0.05       0  5287.7    0.12       0
Bank Sta=4984.7,4994.7
Exp/Cntr=0.3,0.1

Type RM Length L Ch R = 1,37000,500,500,500
BEGIN DESCRIPTION:
FLAG CREEK 74.0
END DESCRIPTION:
XS GIS Cut Line= 3
      2802880.69     10221828.11      2803405.52     10221881.11
      2803885.50     10221778.62
#Sta/Elev= 30
  4472.5 1152.06  4688.6 1141.07  4767.5 1138.00  4867.5 1136.68  4872.6 1136.16
  4879.6 1132.42  4884.5 1124.15  4885.0 1123.65  4894.8 1124.15  4899.7 1127.43
  4919.8 1130.51  4960.0 1124.71  4967.6 1124.93  4980.1 1127.63  5009.8 1124.76
  5014.9 1125.10  5020.6 1127.83  5051.3 1136.17  5071.7 1135.70  5102.4 1129.96
  5108.8 1131.18  5113.9 1130.60  5122.9 1132.67  5133.1 1137.89  5153.2 1139.92
  5296.6 1147.32  5351.3 1148.40  5409.2 1152.31  5439.9 1155.96  5490.8 1157.27
#Mann=3,-1,0
  4472.5    0.05       0  4884.5    0.05       0  4894.8    0.05       0
Bank Sta=4884.5,4894.8
Exp/Cntr=0.3,0.1

Type RM Length L Ch R = 1,36500,500,500,500
BEGIN DESCRIPTION:
FLAG CREEK 73.0
END DESCRIPTION:
XS GIS Cut Line= 3
      2803155.68     10222603.12      2803361.65     10222345.67
      2803755.71     10222153.10
#Sta/Elev= 30
  4670.3 1149.90  4741.5 1145.54  4762.4 1144.92  4770.4 1143.89  4776.8 1144.05
  4784.8 1142.79  4807.0 1141.20  4851.4 1138.44  4869.6 1136.58  4912.8 1133.95
  4919.2 1132.53  4933.6 1124.63  4940.0 1124.21  4948.0 1125.13  4954.4 1127.08
  4962.4 1128.23  4976.9 1128.68  4985.3 1121.99  4985.8 1121.49  4995.6 1121.99
  5013.6 1124.35  5041.7 1126.36  5049.0 1129.46  5081.2 1133.58  5154.3 1133.40
  5186.1 1135.09  5327.3 1139.85  5357.0 1142.12  5407.6 1144.32  5438.6 1146.94
#Mann=6,-1,0
  4670.3    0.12       0  4807.0    0.05       0  4851.4    0.12       0
  4985.3    0.07       0  4995.6    0.12       0  5186.1    0.05       0
Bank Sta=4985.3,4995.6
Exp/Cntr=0.3,0.1

Type RM Length L Ch R = 1,36000,500,500,500
BEGIN DESCRIPTION:
FLAG CREEK 72.0
END DESCRIPTION:
XS GIS Cut Line= 3
      2803255.71     10223003.09      2803778.87     10222595.01
      2804005.70     10222103.08
#Sta/Elev= 30
  4336.5 1168.94  4364.5 1167.97  4472.2 1156.77  4541.6 1152.19  4600.6 1147.35
  4642.2 1146.01  4664.8 1143.33  4753.8 1138.97  4820.4 1135.60  4859.3 1131.25
  4913.6 1128.09  4963.3 1128.63  4977.8 1126.25  4992.3 1119.21  5000.1 1117.75
  5000.6 1117.25  5011.9 1117.75  5013.1 1119.58  5035.1 1124.03  5051.9 1129.98
  5074.8 1131.83  5137.0 1133.16  5292.4 1138.93  5354.5 1144.02  5395.4 1149.85
  5412.7 1151.06  5420.5 1153.70  5458.6 1156.31  5504.5 1161.72  5541.7 1162.20
#Mann=8,-1,0
  4336.5    0.05       0  4541.6    0.12       0  4753.8    0.05       0
  4859.3    0.12       0  5000.1    0.07       0  5011.9    0.12       0
  5137.0    0.05       0  5395.4    0.12       0
Bank Sta=5000.1,5011.9
Exp/Cntr=0.3,0.1

Type RM Length L Ch R = 1,35500,642,642,642
BEGIN DESCRIPTION:
FLAG CREEK 71.0
END DESCRIPTION:
XS GIS Cut Line= 3
      2803905.66     10223053.12      2804120.70     10222942.12
      2804205.69     10222603.11
#Sta/Elev= 30
  4758.0 1147.31  4766.3 1147.76  4780.5 1146.08  4788.4 1143.78  4803.0 1142.93
  4825.5 1143.18  4832.7 1141.51  4838.4 1141.29  4860.5 1135.57  4927.0 1128.48
  4937.9 1128.33  4960.0 1125.80  4988.4 1116.47  4988.9 1115.97  5000.3 1116.47
  5009.3 1118.06  5019.6 1121.72  5029.9 1121.41  5050.5 1123.15  5071.1 1123.76
  5079.2 1125.21  5084.4 1125.09  5091.8 1126.73  5126.6 1127.61  5166.8 1129.01
  5236.1 1133.64  5244.0 1134.81  5277.3 1136.58  5339.2 1142.82  5349.5 1143.05
#Mann=4,-1,0
  4758.0    0.12       0  4988.4    0.07       0  5000.3    0.12       0
  5126.6    0.05       0
Bank Sta=4988.4,5000.3
Exp/Cntr=0.3,0.1

Type RM Length L Ch R = 1,34858,358,358,358
BEGIN DESCRIPTION:
Mapping XS 6e5e9d1e
END DESCRIPTION:
XS GIS Cut Line= 3
      2803746.61     10223229.98      2804142.48     10223507.78
      2804571.85     10223549.33
#Sta/Elev= 30
  4669.5 1149.15  4706.1 1147.34  4736.8 1143.44  4765.3 1141.60  4771.5 1142.13
  4778.3 1140.56  4836.8 1134.21  4872.6 1130.99  4912.6 1129.07  4964.9 1126.70
  4973.6 1125.44  4988.6 1114.00  4989.1 1113.50  5000.6 1114.00  5015.5 1116.38
  5078.1 1121.17  5158.9 1124.33  5254.4 1129.70  5332.9 1134.13  5357.3 1135.22
  5387.4 1138.70  5417.6 1139.69  5457.7 1143.97  5470.4 1144.42  5497.9 1149.17
  5518.0 1149.36  5548.2 1152.45  5558.2 1152.29  5572.5 1154.90  5584.5 1155.05
#Mann=8,-1,0
  4669.5    0.05       0  4736.8    0.12       0  4912.6    0.05       0
  4988.6    0.05       0  5000.6    0.05       0  5078.1    0.12       0
  5254.4    0.05       0  5332.9    0.12       0
Bank Sta=4988.6,5000.6
Exp/Cntr=0.3,0.1

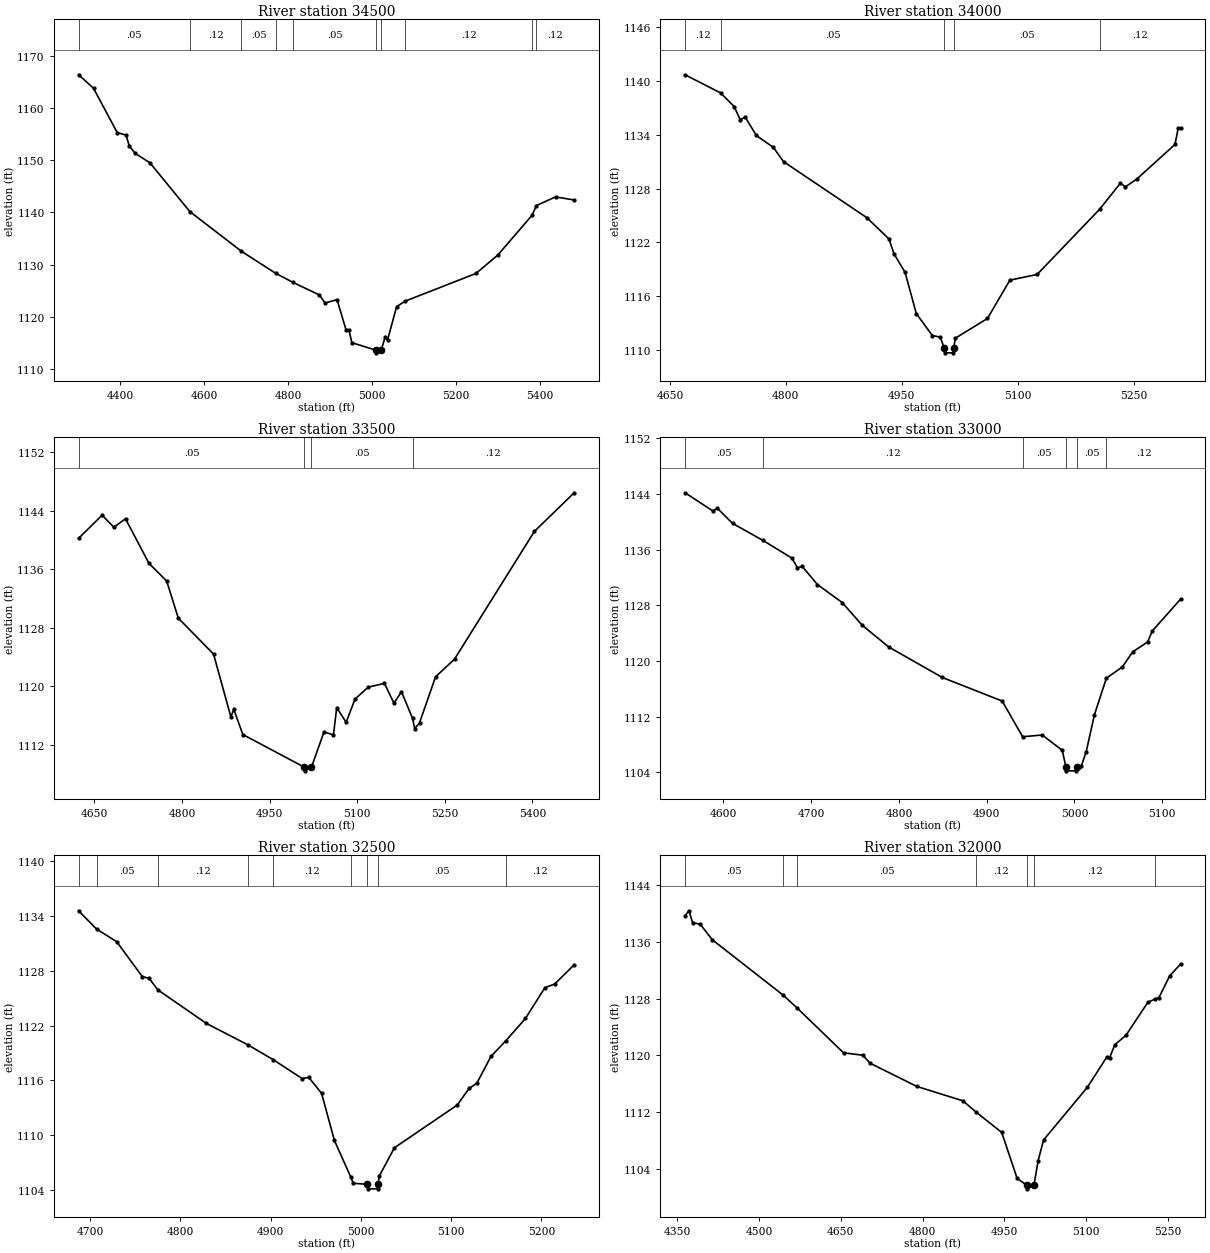
Type RM Length L Ch R = 1,34500,500,500,500
BEGIN DESCRIPTION:
FLAG CREEK 69.0
END DESCRIPTION:
XS GIS Cut Line= 3
      2803405.68     10223253.11      2803895.55     10223750.62
      2804305.66     10224003.10
#Sta/Elev= 30
  4301.8 1166.38  4337.2 1163.80  4393.7 1155.30  4414.9 1154.82  4422.0 1152.80
  4436.2 1151.33  4471.5 1149.51  4566.4 1140.17  4689.5 1132.54  4770.8 1128.33
  4812.2 1126.58  4874.6 1124.19  4888.8 1122.64  4917.0 1123.28  4938.2 1117.55
  4945.3 1117.49  4952.3 1115.03  5010.0 1113.58  5010.5 1113.08  5022.0 1113.58
  5031.4 1116.04  5037.3 1115.55  5058.9 1121.95  5079.5 1123.00  5247.9 1128.30
  5300.0 1131.84  5381.5 1139.47  5391.8 1141.32  5437.2 1142.97  5481.6 1142.38
#Mann=10,-1,0
  4301.8    0.05       0  4566.4    0.12       0  4689.5    0.05       0
  4770.8    0.12       0  4812.2    0.05       0  5010.0    0.05       0
  5022.0    0.05       0  5079.5    0.12       0  5381.5    0.05       0
  5391.8    0.12       0
Bank Sta=5010,5022
Exp/Cntr=0.3,0.1

Type RM Length L Ch R = 1,34000,500,500,500
BEGIN DESCRIPTION:
FLAG CREEK 68.0
END DESCRIPTION:
XS GIS Cut Line= 3
      2803705.71     10224503.08      2803909.55     10224243.19
      2804155.70     10224053.10
#Sta/Elev= 30
  4669.7 1140.65  4715.7 1138.63  4733.2 1137.12  4741.1 1135.64  4747.4 1135.96
  4761.9 1133.90  4784.0 1132.57  4797.1 1130.99  4904.7 1124.77  4933.6 1122.39
  4940.0 1120.75  4954.4 1118.67  4968.9 1114.10  4989.7 1111.65  5000.0 1111.48
  5005.1 1110.23  5005.6 1109.73  5016.8 1109.73  5017.3 1110.23  5019.4 1111.36
  5061.0 1113.55  5090.0 1117.81  5125.3 1118.45  5206.0 1125.68  5233.1 1128.60
  5239.4 1128.18  5253.9 1129.03  5303.7 1132.90  5307.8 1134.71  5311.0 1134.71
#Mann=5,-1,0
  4669.7    0.12       0  4715.7    0.05       0  5005.1    0.05       0
  5017.3    0.05       0  5206.0    0.12       0
Bank Sta=5005.1,5017.3
Exp/Cntr=0.3,0.1

Type RM Length L Ch R = 1,33500,500,500,500
BEGIN DESCRIPTION:
FLAG CREEK 67.0
END DESCRIPTION:
XS GIS Cut Line= 3
      2804305.69     10224853.10      2804341.22     10224477.68
      2804755.69     10224253.11
#Sta/Elev= 30
  4622.9 1140.21  4663.1 1143.36  4683.2 1141.72  4703.2 1142.87  4743.4 1136.78
  4773.6 1134.39  4793.6 1129.31  4853.9 1124.41  4883.6 1115.84  4888.6 1116.86
  4904.1 1113.43  5009.3 1108.98  5009.8 1108.48  5021.6 1108.98  5043.0 1113.78
  5059.2 1113.39  5064.8 1117.09  5081.0 1115.11  5096.1 1118.27  5118.8 1119.90
  5146.6 1120.41  5162.8 1117.71  5175.7 1119.27  5194.6 1115.65  5198.4 1114.24
  5206.6 1115.03  5234.1 1121.31  5266.5 1123.72  5403.4 1141.16  5471.4 1146.42
#Mann=4,-1,0
  4622.9    0.05       0  5009.3    0.05       0  5021.6    0.05       0
  5194.6    0.12       0
Bank Sta=5009.3,5021.6
Exp/Cntr=0.3,0.1

Type RM Length L Ch R = 1,33000,500,500,500
BEGIN DESCRIPTION:
FLAG CREEK 66.0
END DESCRIPTION:
XS GIS Cut Line= 3
      2804605.70     10225003.07      2804794.88     10224601.83
      2804905.64     10224553.13
#Sta/Elev= 30
  4556.4 1144.16  4587.8 1141.57  4593.3 1141.92  4610.5 1139.76  4645.1 1137.32
  4678.0 1134.79  4684.4 1133.40  4689.9 1133.58  4707.2 1130.98  4735.5 1128.39
  4758.3 1125.12  4788.5 1122.01  4849.4 1117.64  4917.7 1114.25  4941.0 1109.12
  4963.3 1109.38  4986.1 1107.18  4990.4 1104.73  4990.9 1104.23  5002.2 1104.23
  5002.7 1104.73  5007.8 1104.91  5013.3 1106.92  5022.7 1112.25  5036.4 1117.54
  5054.5 1119.14  5066.4 1121.31  5083.3 1122.73  5088.8 1124.33  5121.0 1128.90
#Mann=6,-1,0
  4556.4    0.05       0  4645.1    0.12       0  4941.0    0.05       0
  4990.4    0.05       0  5002.7    0.05       0  5036.4    0.12       0
Bank Sta=4990.4,5002.7
Exp/Cntr=0.3,0.1

Type RM Length L Ch R = 1,32500,500,500,500
BEGIN DESCRIPTION:
FLAG CREEK 65.0
END DESCRIPTION:
XS GIS Cut Line= 3
      2804905.71     10225203.08      2805116.38     10224972.00
      2805205.68     10224753.12
#Sta/Elev= 30
  4687.3 1134.58  4707.1 1132.58  4729.5 1131.19  4757.9 1127.36  4765.3 1127.19
  4775.0 1125.92  4828.8 1122.24  4875.4 1119.86  4903.0 1118.26  4934.9 1116.20
  4942.3 1116.32  4956.5 1114.58  4970.7 1109.42  4988.9 1105.39  4991.6 1104.72
  5007.0 1104.61  5007.5 1104.11  5018.8 1104.11  5019.3 1104.61  5020.4 1105.50
  5037.2 1108.61  5106.8 1113.29  5120.1 1115.13  5128.4 1115.66  5144.2 1118.62
  5160.8 1120.35  5182.4 1122.78  5204.0 1126.16  5214.8 1126.55  5236.4 1128.66
#Mann=9,-1,0
  4687.3    0.12       0  4707.1    0.05       0  4775.0    0.12       0
  4875.4    0.05       0  4903.0    0.12       0  4988.9    0.05       0
  5007.0    0.05       0  5019.3    0.05       0  5160.8    0.12       0
Bank Sta=5007,5019.3
Exp/Cntr=0.3,0.1

Type RM Length L Ch R = 1,32000,500,500,500
BEGIN DESCRIPTION:
FLAG CREEK 64.0
END DESCRIPTION:
XS GIS Cut Line= 3
      2805055.71     10225653.09      2805533.60     10225233.58
      2805805.70     10225203.11
#Sta/Elev= 30
  4364.1 1139.68  4371.2 1140.36  4377.8 1138.71  4392.1 1138.45  4413.9 1136.29
  4544.7 1128.45  4569.8 1126.67  4654.9 1120.37  4690.0 1120.03  4704.3 1118.88
  4789.6 1115.63  4874.1 1113.61  4897.4 1112.08  4945.3 1109.16  4973.7 1102.68
  4991.6 1101.72  4992.1 1101.22  5004.5 1101.72  5012.2 1105.19  5022.2 1108.10
  5102.7 1115.53  5138.5 1119.80  5143.5 1119.69  5153.0 1121.51  5173.2 1122.81
  5213.4 1127.45  5227.4 1127.97  5233.7 1128.10  5253.7 1131.20  5273.8 1132.87
#Mann=7,-1,0
  4364.1    0.05       0  4544.7    0.12       0  4569.8    0.05       0
  4897.4    0.12       0  4991.6    0.07       0  5004.5    0.12       0
  5227.4    0.05       0
Bank Sta=4991.6,5004.5
Exp/Cntr=0.3,0.1

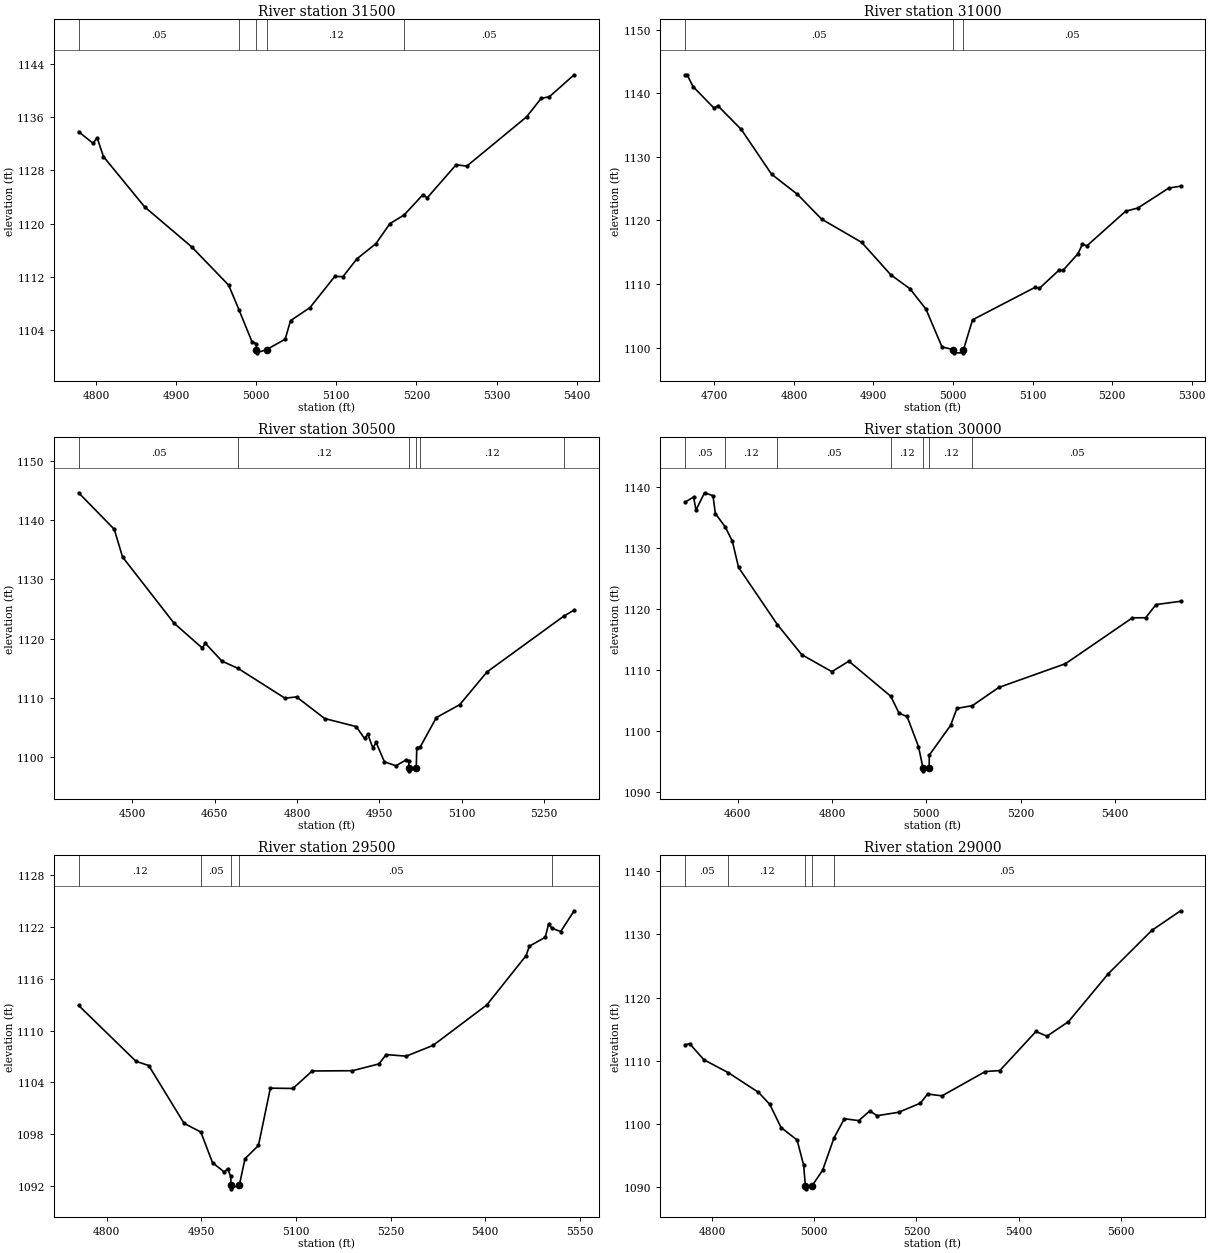
Type RM Length L Ch R = 1,31500,500,500,500
BEGIN DESCRIPTION:
FLAG CREEK 63.0
END DESCRIPTION:
XS GIS Cut Line= 3
      2805205.66     10225653.11      2805420.51     10225707.41
      2805805.69     10225803.11
#Sta/Elev= 30
  4778.4 1133.81  4796.4 1132.06  4801.5 1132.90  4809.4 1130.06  4860.9 1122.49
  4919.5 1116.49  4965.7 1110.72  4978.7 1106.98  4994.9 1102.19  5000.0 1101.94
  5000.3 1101.05  5000.8 1100.55  5013.2 1101.05  5036.2 1102.60  5042.9 1105.39
  5067.2 1107.36  5098.1 1112.04  5108.4 1112.01  5125.6 1114.67  5149.6 1116.99
  5166.9 1119.98  5184.7 1121.28  5208.3 1124.36  5213.4 1123.85  5249.6 1128.84
  5262.9 1128.63  5337.5 1136.04  5355.7 1138.81  5366.0 1139.07  5396.9 1142.37
#Mann=5,-1,0
  4778.4    0.05       0  4978.7    0.12       0  5000.3    0.07       0
  5013.2    0.12       0  5184.7    0.05       0
Bank Sta=5000.3,5013.2
Exp/Cntr=0.3,0.1

Type RM Length L Ch R = 1,31000,500,500,500
BEGIN DESCRIPTION:
FLAG CREEK 62.0
END DESCRIPTION:
XS GIS Cut Line= 3
      2805005.65     10226153.11      2805339.38     10226198.48
      2805605.66     10226303.10
#Sta/Elev= 30
  4663.2 1142.90  4665.8 1142.90  4673.3 1141.03  4699.5 1137.67  4704.5 1138.02
  4733.9 1134.30  4771.9 1127.27  4804.5 1124.10  4834.8 1120.21  4885.3 1116.54
  4921.8 1111.45  4945.8 1109.27  4966.0 1106.06  4986.2 1100.11  5000.3 1099.68
  5000.8 1099.18  5012.7 1099.18  5013.2 1099.68  5024.6 1104.37  5103.2 1109.48
  5108.6 1109.31  5133.0 1112.15  5138.4 1112.16  5157.2 1114.78  5162.8 1116.29
  5168.2 1115.99  5217.0 1121.44  5232.4 1121.95  5271.2 1125.08  5286.1 1125.39
#Mann=3,-1,0
  4663.2    0.05       0  5000.3    0.05       0  5013.2    0.05       0
Bank Sta=5000.3,5013.2
Exp/Cntr=0.3,0.1

Type RM Length L Ch R = 1,30500,500,500,500
BEGIN DESCRIPTION:
FLAG CREEK 61.0
END DESCRIPTION:
XS GIS Cut Line= 3
      2804905.70     10226353.12      2805407.11     10226679.18
      2805655.67     10226503.12
#Sta/Elev= 30
  4401.9 1144.59  4466.8 1138.44  4481.9 1133.77  4575.5 1122.64  4626.9 1118.44
  4632.8 1119.22  4663.1 1116.21  4692.5 1114.99  4777.8 1109.97  4798.9 1110.19
  4850.2 1106.54  4907.6 1105.19  4922.7 1103.18  4928.7 1103.91  4937.9 1101.57
  4943.8 1102.51  4959.0 1099.24  4980.1 1098.59  4999.0 1099.61  5003.1 1099.45
  5004.0 1098.23  5004.5 1097.73  5017.0 1098.23  5017.9 1101.63  5024.2 1101.75
  5053.6 1106.71  5096.3 1108.89  5145.8 1114.39  5285.3 1123.77  5304.6 1124.83
#Mann=6,-1,0
  4401.9    0.05       0  4692.5    0.12       0  5004.0    0.07       0
  5017.0    0.12       0  5024.2    0.12       0  5285.3    0.05       0
Bank Sta=5004,5017
Exp/Cntr=0.3,0.1

Type RM Length L Ch R = 1,30000,500,500,500
BEGIN DESCRIPTION:
FLAG CREEK 60.0
END DESCRIPTION:
XS GIS Cut Line= 3
      2805005.66     10227253.12      2805501.86     10227128.56
      2805755.71     10226653.07
#Sta/Elev= 30
  4488.4 1137.44  4506.4 1138.28  4511.6 1136.15  4529.7 1138.98  4547.6 1138.50
  4552.7 1135.56  4573.6 1133.39  4588.7 1131.03  4601.8 1126.75  4684.1 1117.37
  4735.9 1112.43  4799.7 1109.65  4835.7 1111.37  4924.5 1105.62  4942.1 1102.83
  4959.1 1102.30  4983.3 1097.38  4992.8 1093.89  4993.3 1093.39  5006.0 1093.89
  5006.2 1095.96  5051.5 1100.86  5064.9 1103.63  5097.6 1104.08  5153.5 1107.06
  5295.0 1110.96  5436.9 1118.48  5465.0 1118.49  5486.9 1120.65  5539.0 1121.19
#Mann=7,-1,0
  4488.4    0.05       0  4573.6    0.12       0  4684.1    0.05       0
  4924.5    0.12       0  4992.8    0.07       0  5006.0    0.12       0
  5097.6    0.05       0
Bank Sta=4992.8,5006
Exp/Cntr=0.3,0.1

Type RM Length L Ch R = 1,29500,500,500,500
BEGIN DESCRIPTION:
FLAG CREEK 59.0
END DESCRIPTION:
XS GIS Cut Line= 3
      2805905.68     10227353.11      2805942.16     10227111.14
      2805755.67     10226603.09
#Sta/Elev= 30
  4755.3 1112.92  4846.3 1106.44  4866.5 1105.95  4922.6 1099.24  4949.1 1098.24
  4967.7 1094.68  4986.5 1093.59  4991.5 1093.99  4996.5 1093.10  4997.1 1092.15
  4997.6 1091.65  5010.4 1092.15  5019.2 1095.15  5040.5 1096.68  5059.4 1103.33
  5095.2 1103.29  5125.7 1105.32  5189.6 1105.35  5231.7 1106.14  5242.9 1107.22
  5274.9 1107.04  5317.5 1108.29  5402.7 1112.98  5464.9 1118.69  5470.3 1119.80
  5495.4 1120.83  5500.8 1122.40  5505.8 1121.88  5519.9 1121.49  5541.2 1123.90
#Mann=5,-1,0
  4755.3    0.12       0  4949.1    0.05       0  4997.1    0.05       0
  5010.4    0.05       0  5505.8    0.12       0
Bank Sta=4997.1,5010.4
Exp/Cntr=0.3,0.1

Type RM Length L Ch R = 1,29000,500,500,500
BEGIN DESCRIPTION:
FLAG CREEK 58.0
END DESCRIPTION:
XS GIS Cut Line= 3
      2806455.69     10227053.13      2806348.00     10226824.42
      2805855.70     10226303.13
#Sta/Elev= 30
  4747.2 1112.48  4755.9 1112.69  4784.2 1110.12  4832.0 1108.07  4890.9 1104.96
  4913.0 1103.05  4935.1 1099.38  4966.5 1097.39  4979.3 1093.39  4982.6 1090.15
  4983.1 1089.65  4995.9 1090.15  5016.5 1092.61  5038.7 1097.73  5059.0 1100.77
  5087.3 1100.47  5108.8 1102.02  5122.9 1101.25  5165.4 1101.80  5207.9 1103.25
  5221.9 1104.69  5250.0 1104.40  5334.9 1108.26  5363.2 1108.41  5434.0 1114.61
  5455.5 1113.87  5497.6 1116.17  5575.6 1123.78  5660.6 1130.64  5717.0 1133.76
#Mann=5,-1,0
  4747.2    0.05       0  4832.0    0.12       0  4982.6    0.07       0
  4995.9    0.12       0  5038.7    0.05       0
Bank Sta=4982.6,4995.9
Exp/Cntr=0.3,0.1

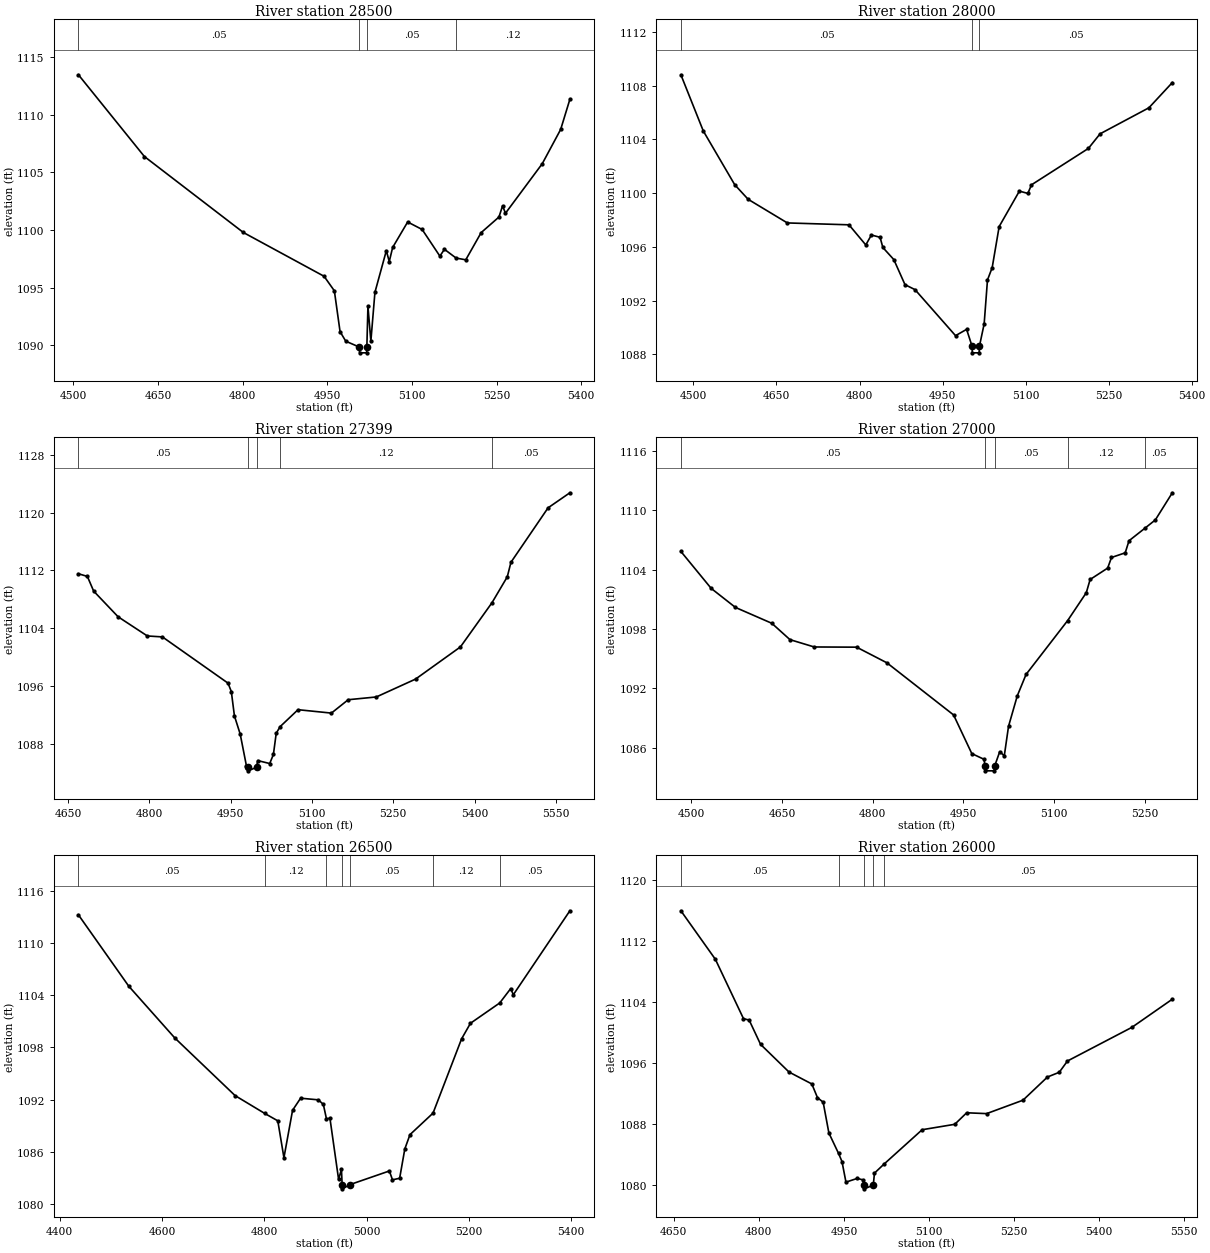
Type RM Length L Ch R = 1,28500,500,500,500
BEGIN DESCRIPTION:
FLAG CREEK 57.0
END DESCRIPTION:
XS GIS Cut Line= 3
      2806755.68     10226953.06      2806693.21     10226465.95
      2806805.69     10226103.09
#Sta/Elev= 30
  4508.9 1113.47  4625.8 1106.38  4801.2 1099.79  4944.3 1095.99  4962.5 1094.73
  4972.6 1091.19  4982.7 1090.36  5006.7 1089.85  5007.2 1089.35  5019.6 1089.35
  5020.1 1089.85  5022.0 1093.40  5027.2 1090.36  5034.4 1094.60  5054.6 1098.21
  5059.8 1097.27  5065.8 1098.49  5092.4 1100.70  5118.1 1100.05  5149.5 1097.74
  5157.6 1098.33  5178.3 1097.57  5195.4 1097.42  5222.7 1099.78  5254.2 1101.13
  5260.6 1102.10  5265.8 1101.46  5331.0 1105.76  5363.6 1108.73  5379.9 1111.34
#Mann=4,-1,0
  4508.9    0.05       0  5006.7    0.05       0  5020.1    0.05       0
  5178.3    0.12       0
Bank Sta=5006.7,5020.1
Exp/Cntr=0.3,0.1

Type RM Length L Ch R = 1,28000,601,601,601
BEGIN DESCRIPTION:
FLAG CREEK 56.0
END DESCRIPTION:
XS GIS Cut Line= 3
      2807055.68     10226903.16      2807135.49     10226386.59
      2807330.66     10226078.15
#Sta/Elev= 30
  4477.3 1108.82  4517.8 1104.63  4574.5 1100.63  4598.8 1099.54  4669.6 1097.78
  4780.9 1097.64  4811.3 1096.14  4821.4 1096.88  4837.1 1096.71  4842.1 1095.95
  4861.9 1095.05  4882.1 1093.18  4900.2 1092.81  4973.4 1089.38  4993.4 1089.85
  5003.2 1088.60  5003.7 1088.10  5016.1 1088.10  5016.6 1088.60  5025.1 1090.26
  5031.1 1093.53  5039.6 1094.45  5052.2 1097.51  5088.7 1100.15  5104.0 1099.98
  5110.6 1100.62  5213.3 1103.33  5234.5 1104.42  5322.7 1106.36  5365.0 1108.24
#Mann=3,-1,0
  4477.3    0.05       0  5003.2    0.03       0  5016.6    0.05       0
Bank Sta=5003.2,5016.6
Exp/Cntr=0.3,0.1

Type RM Length L Ch R = 1,27399,399,399,399
BEGIN DESCRIPTION:
FLAG CREEK 55.0
END DESCRIPTION:
XS GIS Cut Line= 3
      2807180.71     10227028.10      2807474.25     10226876.00
      2808030.73     10226728.10
#Sta/Elev= 30
  4669.4 1111.54  4685.9 1111.17  4697.5 1109.14  4742.6 1105.59  4796.5 1102.94
  4824.3 1102.81  4945.3 1096.42  4951.4 1095.26  4957.1 1091.90  4967.8 1089.37
  4979.2 1085.01  4982.2 1084.80  4982.7 1084.30  4998.0 1084.80  5000.0 1085.72
  5022.2 1085.31  5029.0 1086.56  5034.2 1089.49  5041.3 1090.40  5074.4 1092.75
  5136.0 1092.28  5167.0 1094.13  5218.8 1094.51  5291.2 1096.98  5374.0 1101.43
  5432.2 1107.54  5460.4 1111.12  5467.1 1113.12  5535.6 1120.65  5575.8 1122.73
#Mann=5,-1,0
  4669.4    0.05       0  4982.2    0.03       0  4998.0    0.05       0
  5041.3    0.12       0  5432.2    0.05       0
Bank Sta=4982.2,4998
Exp/Cntr=0.3,0.1

Type RM Length L Ch R = 1,27000,500,500,500
BEGIN DESCRIPTION:
FLAG CREEK 54.0
END DESCRIPTION:
XS GIS Cut Line= 3
      2807255.65     10227103.11      2807771.76     10227133.51
      2808005.68     10226953.11
#Sta/Elev= 30
  4483.0 1105.83  4533.1 1102.10  4573.2 1100.18  4633.3 1098.58  4663.3 1096.93
  4703.4 1096.19  4773.5 1096.17  4823.6 1094.59  4933.8 1089.33  4963.9 1085.43
  4983.9 1084.86  4986.0 1084.19  4986.5 1083.69  5001.3 1083.69  5001.8 1084.19
  5010.1 1085.63  5017.6 1085.20  5024.6 1088.18  5039.1 1091.26  5053.6 1093.42
  5122.3 1098.85  5153.2 1101.67  5159.5 1103.00  5188.5 1104.15  5194.8 1105.22
  5217.5 1105.69  5223.8 1106.91  5250.6 1108.20  5267.3 1109.01  5295.4 1111.75
#Mann=5,-1,0
  4483.0    0.05       0  4986.0    0.03       0  5001.8    0.05       0
  5122.3    0.12       0  5250.6    0.05       0
Bank Sta=4986,5001.8
Exp/Cntr=0.3,0.1

Type RM Length L Ch R = 1,26500,500,500,500
BEGIN DESCRIPTION:
FLAG CREEK 53.0
END DESCRIPTION:
XS GIS Cut Line= 3
      2807055.64     10227803.13      2807561.50     10227554.85
      2807955.72     10227503.11
#Sta/Elev= 30
  4436.5 1113.29  4535.0 1105.06  4624.9 1099.10  4742.9 1092.45  4800.4 1090.41
  4826.4 1089.54  4838.4 1085.29  4855.3 1090.76  4871.0 1092.15  4905.9 1091.96
  4915.5 1091.43  4921.5 1089.79  4928.4 1089.83  4945.3 1082.79  4950.9 1083.95
  4952.2 1082.20  4952.7 1081.70  4968.1 1082.20  5044.6 1083.76  5050.7 1082.74
  5064.7 1082.92  5074.8 1086.30  5084.9 1087.95  5130.0 1090.43  5185.8 1098.99
  5203.2 1100.79  5260.4 1103.13  5281.9 1104.79  5287.0 1104.08  5397.6 1113.76
#Mann=7,-1,0
  4436.5    0.05       0  4800.4    0.12       0  4921.5    0.05       0
  4952.2    0.03       0  4968.1    0.05       0  5130.0    0.12       0
  5260.4    0.05       0
Bank Sta=4952.2,4968.1
Exp/Cntr=0.3,0.1

Type RM Length L Ch R = 1,26000,500,500,500
BEGIN DESCRIPTION:
FLAG CREEK 52.0
END DESCRIPTION:
XS GIS Cut Line= 3
      2807105.72     10228003.12      2807441.90     10228033.03
      2807855.68     10227703.12
#Sta/Elev= 30
  4662.5 1115.95  4723.3 1109.59  4772.9 1101.81  4782.9 1101.62  4803.0 1098.44
  4853.2 1094.81  4893.4 1093.25  4903.4 1091.45  4913.4 1090.86  4923.5 1086.82
  4940.5 1084.15  4946.6 1083.08  4953.6 1080.38  4973.7 1080.87  4983.7 1080.67
  4985.8 1080.00  4986.3 1079.50  5001.8 1080.00  5003.9 1081.56  5020.4 1082.72
  5088.0 1087.25  5145.5 1087.96  5166.5 1089.47  5201.7 1089.36  5265.8 1091.12
  5309.0 1094.16  5329.8 1094.78  5344.3 1096.26  5457.9 1100.67  5529.2 1104.36
#Mann=5,-1,0
  4662.5    0.05       0  4940.5    0.12       0  4985.8    0.07       0
  5001.8    0.12       0  5020.4    0.05       0
Bank Sta=4985.8,5001.8
Exp/Cntr=0.3,0.1

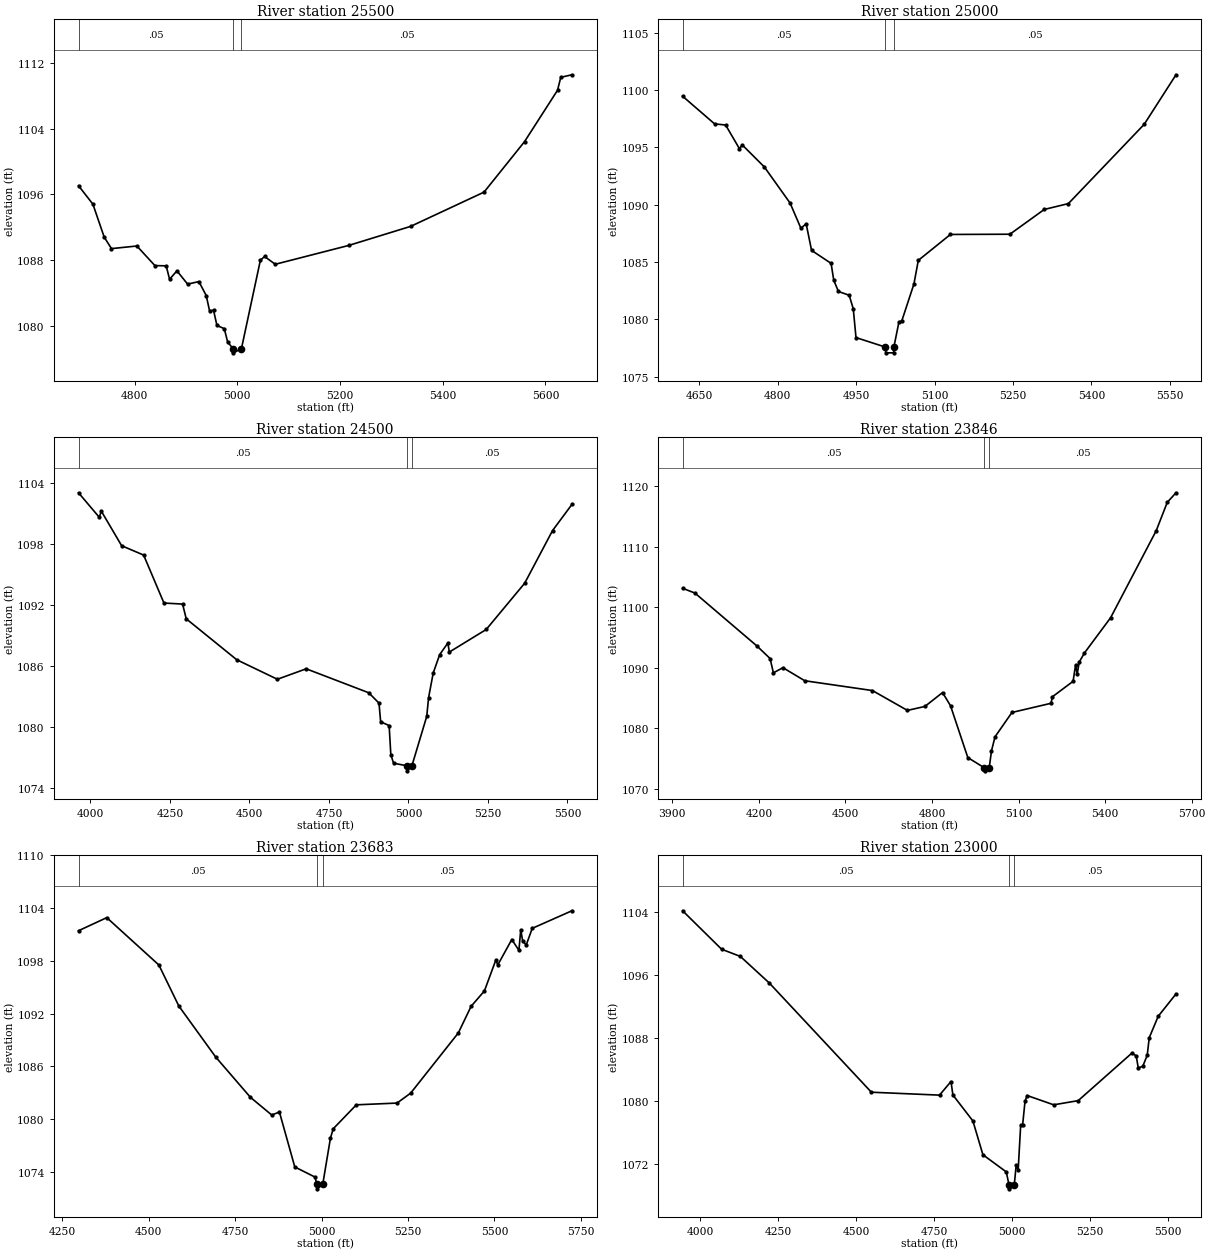
Type RM Length L Ch R = 1,25500,500,500,500
BEGIN DESCRIPTION:
FLAG CREEK 51.0
END DESCRIPTION:
XS GIS Cut Line= 3
      2807555.68     10228603.11      2807756.63     10228368.11
      2808155.68     10227853.12
#Sta/Elev= 30
  4690.8 1097.06  4718.8 1094.81  4740.8 1090.79  4755.0 1089.39  4804.4 1089.71
  4839.5 1087.32  4861.5 1087.29  4868.1 1085.65  4882.4 1086.68  4903.2 1085.06
  4925.2 1085.37  4939.5 1083.66  4946.0 1081.79  4953.7 1081.88  4960.3 1080.02
  4974.6 1079.63  4981.2 1077.99  4991.9 1077.18  4992.4 1076.68  5008.0 1077.18
  5044.9 1087.97  5053.1 1088.43  5073.9 1087.48  5217.0 1089.78  5337.4 1092.10
  5480.4 1096.28  5559.2 1102.43  5623.5 1108.70  5629.8 1110.28  5651.5 1110.59
#Mann=3,-1,0
  4690.8    0.05       0  4991.9    0.03       0  5008.0    0.05       0
Bank Sta=4991.9,5008
Exp/Cntr=0.3,0.1

Type RM Length L Ch R = 1,25000,500,500,500
BEGIN DESCRIPTION:
FLAG CREEK 50.0
END DESCRIPTION:
XS GIS Cut Line= 3
      2807705.68     10228753.11      2808077.13     10228666.13
      2808305.68     10228153.13
#Sta/Elev= 30
  4618.5 1099.45  4679.6 1097.04  4700.7 1096.94  4727.2 1094.87  4732.4 1095.21
  4774.8 1093.28  4823.9 1090.14  4844.5 1087.95  4854.7 1088.32  4865.0 1086.01
  4902.3 1084.88  4907.4 1083.41  4916.3 1082.43  4936.9 1082.10  4944.7 1080.92
  4949.9 1078.41  5006.2 1077.58  5006.7 1077.08  5021.8 1077.08  5022.3 1077.58
  5032.0 1079.77  5037.5 1079.87  5060.7 1083.09  5069.0 1085.14  5130.4 1087.40
  5244.1 1087.42  5309.8 1089.58  5355.9 1090.09  5500.8 1097.00  5561.6 1101.32
#Mann=3,-1,0
  4618.5    0.05       0  5006.2    0.03       0  5022.3    0.05       0
Bank Sta=5006.2,5022.3
Exp/Cntr=0.3,0.1

Type RM Length L Ch R = 1,24500,654,654,654
BEGIN DESCRIPTION:
FLAG CREEK 49.0
END DESCRIPTION:
XS GIS Cut Line= 4
      2807583.66     10228980.67      2808282.36     10228753.46
      2808570.01     10228659.92      2808655.68     10228153.11
#Sta/Elev= 30
  3962.8 1103.05  4028.0 1100.64  4034.5 1101.24  4098.4 1097.84  4167.5 1096.92
  4231.4 1092.20  4290.0 1092.10  4301.4 1090.65  4460.3 1086.62  4588.0 1084.70
  4678.6 1085.73  4875.5 1083.37  4907.5 1082.35  4912.7 1080.51  4939.4 1080.15
  4944.7 1077.27  4953.4 1076.44  4994.9 1076.19  4995.4 1075.69  5011.0 1076.19
  5057.6 1081.05  5063.4 1082.89  5077.9 1085.31  5098.2 1087.12  5123.8 1088.26
  5128.8 1087.38  5244.6 1089.60  5365.5 1094.15  5453.1 1099.33  5514.0 1101.90
#Mann=3,-1,0
  3962.8    0.05       0  4994.9    0.03       0  5011.0    0.05       0
Bank Sta=4994.9,5011
Exp/Cntr=0.3,0.1

Type RM Length L Ch R = 1,23846,163,163,163
BEGIN DESCRIPTION:
Mapping XS 5d1a234c
END DESCRIPTION:
XS GIS Cut Line= 5
      2807655.81     10229088.96      2808034.78     10228894.96
      2808436.29     10229079.93      2808679.90     10229210.76
      2809209.93     10229408.40
#Sta/Elev= 30
  3935.8 1103.14  3978.3 1102.36  4194.0 1093.58  4239.0 1091.53  4250.4 1089.17
  4283.5 1090.02  4359.2 1087.86  4593.7 1086.24  4714.9 1082.96  4775.4 1083.61
  4836.7 1085.91  4864.3 1083.73  4924.3 1075.16  4981.7 1073.47  4982.2 1072.97
  4998.4 1073.47  5006.3 1076.27  5018.6 1078.60  5077.3 1082.62  5212.3 1084.13
  5217.7 1085.22  5289.1 1087.77  5298.0 1090.53  5303.3 1088.93  5310.4 1090.95
  5328.3 1092.44  5419.2 1098.28  5577.2 1112.66  5615.5 1117.35  5645.8 1118.93
#Mann=3,-1,0
  3935.8    0.05       0  4981.7    0.03       0  4998.4    0.05       0
Bank Sta=4981.7,4998.4
Exp/Cntr=0.3,0.1

Type RM Length L Ch R = 1,23683,683,683,683
BEGIN DESCRIPTION:
Mapping XS d724f49a
END DESCRIPTION:
XS GIS Cut Line= 6
      2807849.79     10229337.08      2808219.74     10229246.85
      2808368.62     10229233.31      2808634.79     10229368.65
      2808873.89     10229485.95      2809192.43     10229580.17
#Sta/Elev= 30
  4296.6 1101.42  4378.3 1102.91  4529.1 1097.52  4586.7 1092.86  4693.4 1087.05
  4793.8 1082.47  4855.6 1080.45  4877.8 1080.79  4922.3 1074.54  4980.7 1073.39
  4986.4 1072.55  4986.9 1072.05  5003.1 1072.55  5025.5 1077.84  5033.6 1078.89
  5100.3 1081.61  5218.1 1081.81  5257.5 1082.94  5395.4 1089.79  5432.4 1092.82
  5470.9 1094.57  5504.2 1098.12  5509.4 1097.52  5550.1 1100.42  5570.7 1099.19
  5576.0 1101.54  5581.4 1100.27  5591.8 1099.79  5609.2 1101.69  5724.0 1103.69
#Mann=3,-1,0
  4296.6    0.05       0  4986.4    0.03       0  5003.1    0.05       0
Bank Sta=4986.4,5003.1
Exp/Cntr=0.3,0.1

Type RM Length L Ch R = 1,23000,500,500,500
BEGIN DESCRIPTION:
FLAG CREEK 46.0
END DESCRIPTION:
XS GIS Cut Line= 3
      2807555.72     10230353.10      2808542.83     10229978.50
      2808955.71     10229653.09
#Sta/Elev= 30
  3944.2 1104.16  4069.1 1099.28  4129.4 1098.36  4222.3 1094.98  4549.3 1081.12
  4767.7 1080.75  4804.5 1082.48  4810.5 1080.77  4874.7 1077.47  4906.8 1073.18
  4981.7 1071.00  4990.4 1069.35  4990.9 1068.85  5007.3 1069.35  5013.4 1071.84
  5019.8 1071.25  5027.8 1076.91  5034.2 1077.02  5041.8 1079.98  5048.6 1080.70
  5133.6 1079.52  5212.2 1080.05  5383.8 1086.07  5398.2 1085.75  5404.6 1084.22
  5419.1 1084.40  5433.5 1085.82  5439.9 1088.04  5468.8 1090.77  5525.7 1093.60
#Mann=3,-1,0
  3944.2    0.05       0  4990.4    0.05       0  5007.3    0.05       0
Bank Sta=4990.4,5007.3
Exp/Cntr=0.3,0.1