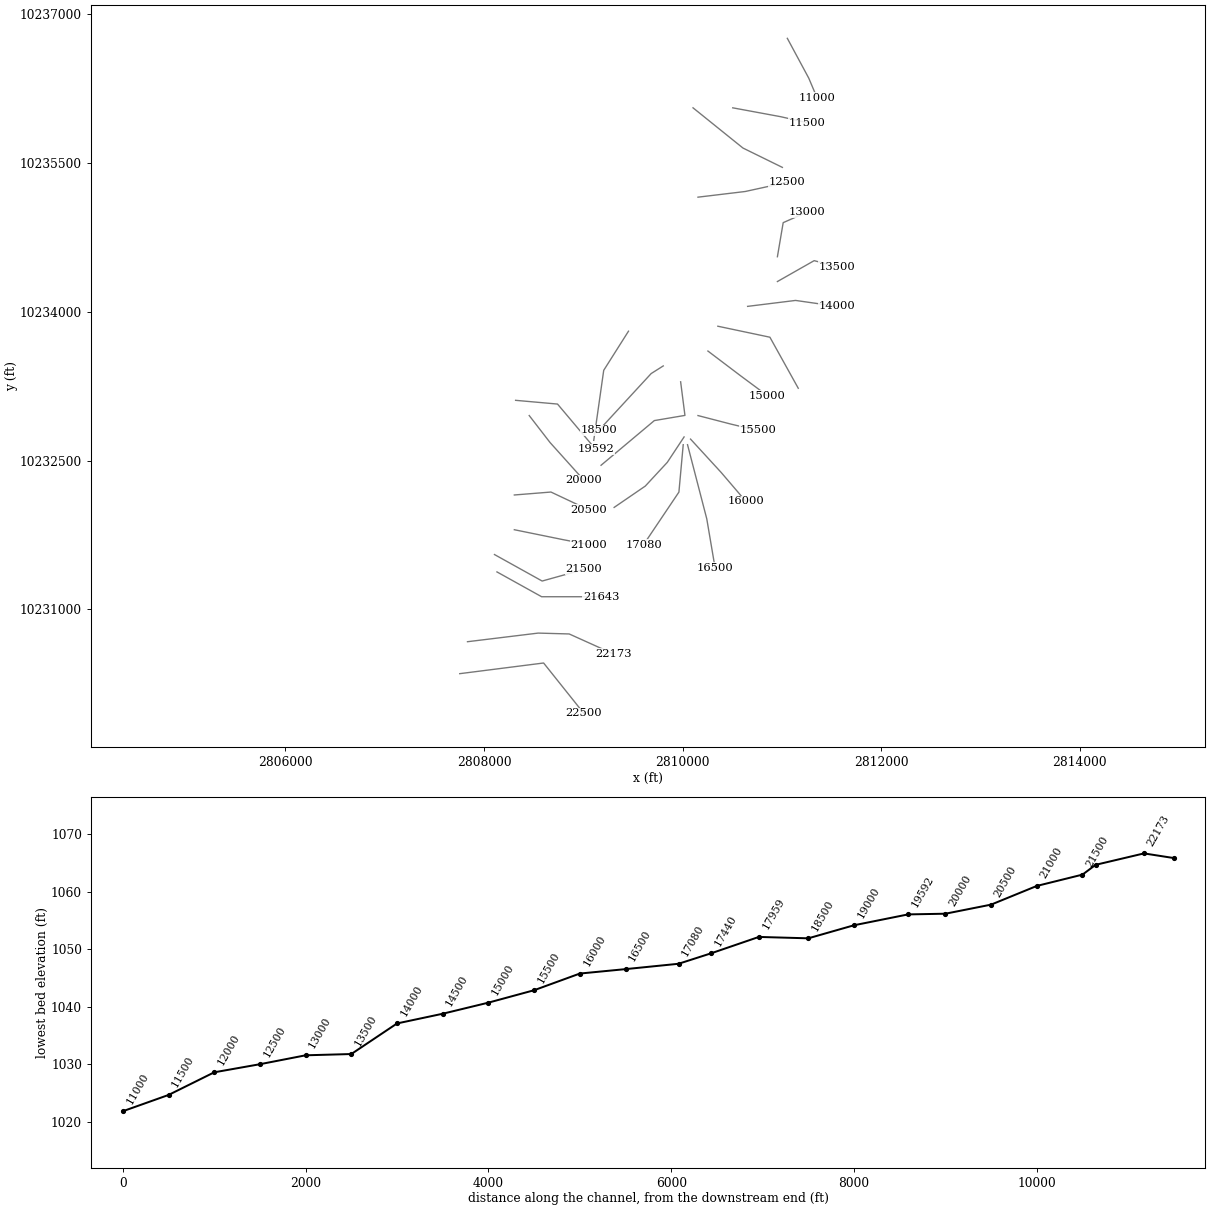
HEC-RAS study FLAG CREEK.prj: FLAG CREEK Base Level Engineering

--- FLAG CREEK.g01 (geometry) --- (continued)

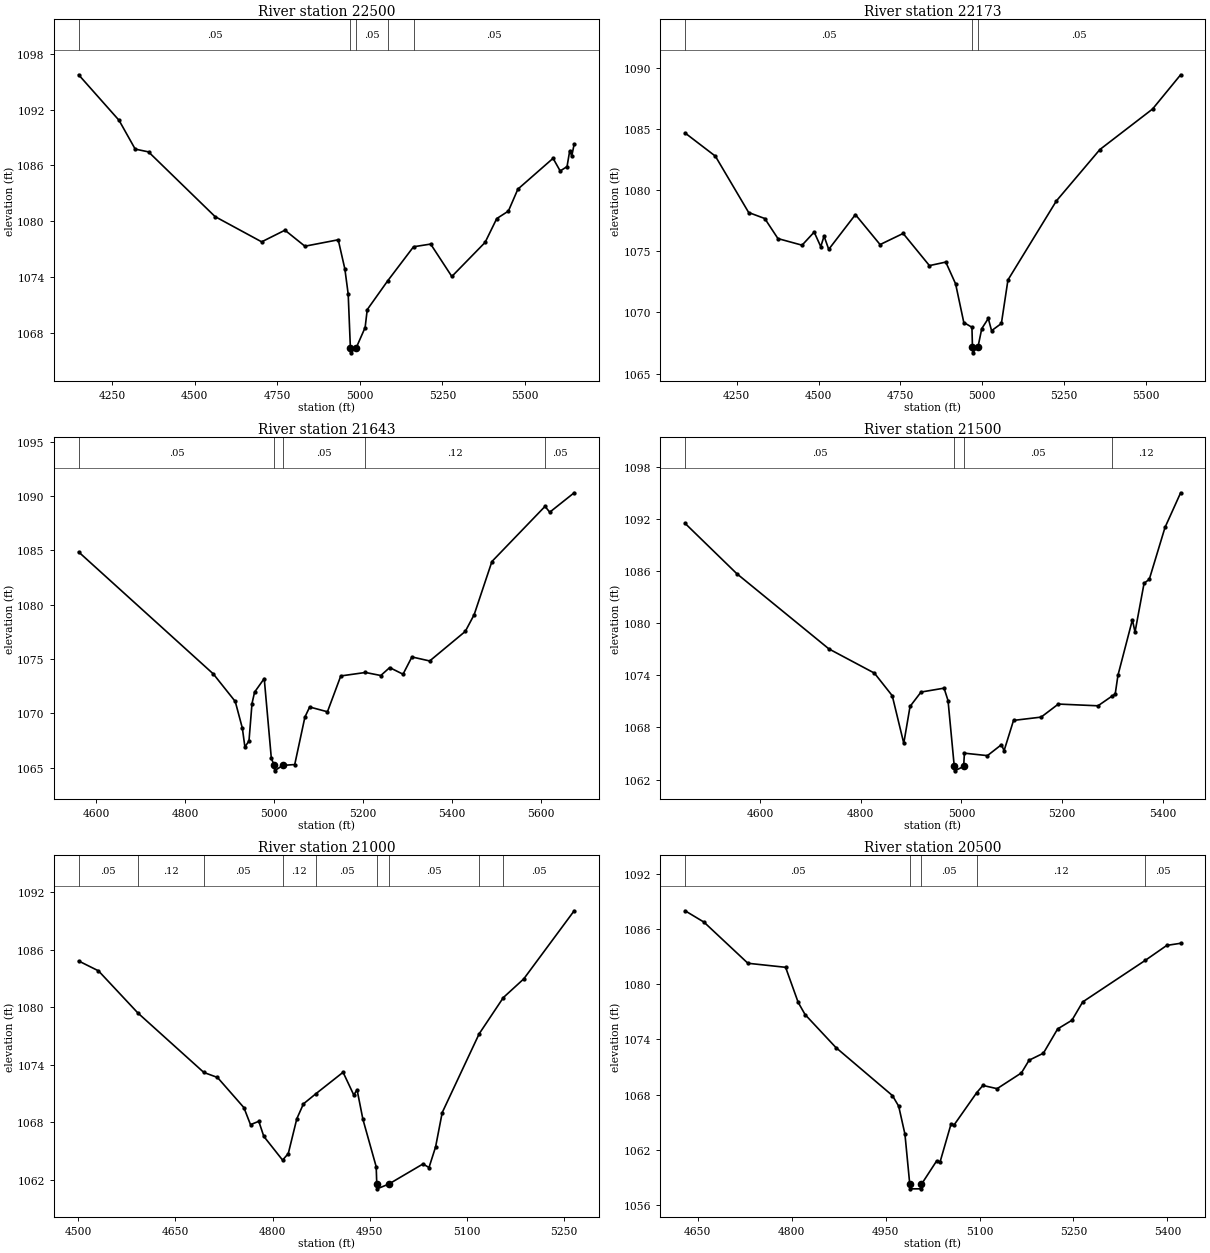
Type RM Length L Ch R = 1,22500,327,327,327
BEGIN DESCRIPTION:
FLAG CREEK 45.0
END DESCRIPTION:
XS GIS Cut Line= 3
      2807755.72     10230353.12      2808600.61     10230460.61
      2809005.66     10229953.14
#Sta/Elev= 30
  4148.3 1095.74  4270.7 1090.85  4319.6 1087.76  4360.0 1087.46  4561.6 1080.51
  4702.7 1077.80  4773.3 1079.05  4833.7 1077.33  4934.6 1078.02  4954.7 1074.89
  4964.8 1072.19  4971.5 1066.38  4972.0 1065.88  4988.6 1066.38  5016.1 1068.60
  5022.5 1070.52  5084.2 1073.60  5162.7 1077.27  5214.6 1077.56  5278.7 1074.08
  5379.5 1077.74  5414.8 1080.30  5450.0 1081.10  5478.8 1083.46  5585.4 1086.77
  5606.9 1085.41  5627.7 1085.88  5635.7 1087.56  5642.1 1087.03  5649.3 1088.30
#Mann=5,-1,0
  4148.3    0.05       0  4971.5    0.05       0  4988.6    0.05       0
  5084.2    0.12       0  5162.7    0.05       0
Bank Sta=4971.5,4988.6
Exp/Cntr=0.3,0.1

Type RM Length L Ch R = 1,22173,530,530,530
BEGIN DESCRIPTION:
Mapping XS 84a7c47c
END DESCRIPTION:
XS GIS Cut Line= 4
      2807833.90     10230675.05      2808545.75     10230761.87
      2808858.25     10230753.18      2809300.79     10230553.61
#Sta/Elev= 30
  4092.1 1084.66  4184.6 1082.77  4286.5 1078.16  4335.7 1077.67  4376.0 1076.03
  4449.7 1075.49  4486.8 1076.56  4506.9 1075.37  4517.0 1076.23  4531.3 1075.15
  4612.9 1077.99  4688.3 1075.54  4758.8 1076.45  4839.2 1073.82  4889.2 1074.11
  4919.2 1072.33  4944.3 1069.17  4969.2 1068.78  4970.7 1067.19  4971.2 1066.69
  4987.8 1067.19  4999.2 1068.67  5019.2 1069.50  5029.2 1068.50  5059.2 1069.09
  5079.3 1072.65  5227.4 1079.11  5360.4 1083.31  5521.4 1086.62  5607.3 1089.42
#Mann=3,-1,0
  4092.1    0.05       0  4970.7    0.05       0  4987.8    0.05       0
Bank Sta=4970.7,4987.8
Exp/Cntr=0.3,0.1

Type RM Length L Ch R = 1,21643,143,143,143
BEGIN DESCRIPTION:
FLAG CREEK 44.0
END DESCRIPTION:
XS GIS Cut Line= 3
      2808130.72     10231378.09      2808580.68     10231128.11
      2809180.64     10231128.11
#Sta/Elev= 30
  4560.7 1084.86  4863.8 1073.62  4913.0 1071.09  4929.0 1068.63  4934.7 1066.90
  4943.9 1067.45  4950.7 1070.90  4956.5 1071.95  4978.2 1073.20  4994.2 1065.84
  5000.9 1065.20  5001.4 1064.70  5019.5 1065.20  5046.8 1065.28  5069.7 1069.65
  5080.4 1070.58  5120.4 1070.14  5150.4 1073.44  5205.9 1073.76  5240.4 1073.48
  5260.4 1074.21  5290.4 1073.60  5310.4 1075.19  5350.4 1074.82  5430.4 1077.54
  5450.4 1079.08  5490.4 1083.98  5609.9 1089.06  5620.4 1088.52  5675.4 1090.31
#Mann=5,-1,0
  4560.7    0.05       0  5000.9    0.05       0  5019.5    0.05       0
  5205.9    0.12       0  5609.9    0.05       0
Bank Sta=5000.9,5019.5
Exp/Cntr=0.3,0.1

Type RM Length L Ch R = 1,21500,500,500,500
BEGIN DESCRIPTION:
FLAG CREEK 43.0
END DESCRIPTION:
XS GIS Cut Line= 3
      2808105.72     10231553.09      2808585.84     10231286.22
      2809005.67     10231403.11
#Sta/Elev= 30
  4450.7 1091.46  4553.6 1085.67  4736.7 1077.02  4827.0 1074.24  4862.5 1071.64
  4885.4 1066.17  4897.9 1070.41  4919.7 1072.06  4965.5 1072.51  4973.4 1071.08
  4985.8 1063.50  4986.3 1063.00  5004.4 1063.50  5006.0 1065.03  5051.7 1064.75
  5079.6 1066.01  5084.8 1065.31  5103.6 1068.80  5158.5 1069.18  5192.7 1070.68
  5271.5 1070.48  5298.8 1071.57  5305.7 1071.82  5311.2 1073.99  5339.9 1080.37
  5345.1 1078.96  5363.1 1084.57  5373.5 1085.03  5404.7 1090.99  5435.8 1094.98
#Mann=4,-1,0
  4450.7    0.05       0  4985.8    0.05       0  5004.4    0.05       0
  5298.8    0.12       0
Bank Sta=4985.8,5004.4
Exp/Cntr=0.3,0.1

Type RM Length L Ch R = 1,21000,500,500,500
BEGIN DESCRIPTION:
FLAG CREEK 42.0
END DESCRIPTION:
XS GIS Cut Line= 3
      2808305.68     10231803.11      2808795.03     10231703.42
      2809055.71     10231653.11
#Sta/Elev= 30
  4500.6 1084.82  4531.2 1083.79  4592.2 1079.38  4693.9 1073.18  4714.9 1072.66
  4755.7 1069.51  4765.9 1067.73  4778.7 1068.08  4786.4 1066.51  4815.4 1064.03
  4824.2 1064.71  4837.4 1068.35  4847.6 1069.90  4867.2 1070.98  4908.8 1073.20
  4925.3 1070.83  4930.4 1071.37  4939.4 1068.29  4959.9 1063.34  4960.8 1061.53
  4961.3 1061.03  4979.4 1061.53  5032.2 1063.63  5041.4 1063.25  5051.6 1065.41
  5061.8 1068.99  5118.8 1077.21  5156.2 1081.00  5187.7 1082.95  5265.5 1090.06
#Mann=9,-1,0
  4500.6    0.05       0  4592.2    0.12       0  4693.9    0.05       0
  4815.4    0.12       0  4867.2    0.05       0  4960.8    0.05       0
  4979.4    0.05       0  5118.8    0.12       0  5156.2    0.05       0
Bank Sta=4960.8,4979.4
Exp/Cntr=0.3,0.1

Type RM Length L Ch R = 1,20500,500,500,500
BEGIN DESCRIPTION:
FLAG CREEK 41.0
END DESCRIPTION:
XS GIS Cut Line= 3
      2808305.68     10232153.11      2808674.69     10232182.72
      2809055.68     10232003.11
#Sta/Elev= 30
  4629.8 1087.98  4659.9 1086.75  4730.1 1082.28  4790.3 1081.84  4810.4 1078.03
  4821.4 1076.71  4870.6 1073.13  4960.9 1067.91  4970.9 1066.76  4980.9 1063.72
  4988.6 1058.28  4989.1 1057.78  5006.8 1057.78  5007.3 1058.28  5031.5 1060.81
  5037.0 1060.70  5054.3 1064.77  5059.8 1064.76  5095.7 1068.24  5105.4 1069.01
  5128.1 1068.66  5166.9 1070.37  5179.2 1071.75  5202.0 1072.51  5224.8 1075.15
  5247.6 1076.09  5264.8 1078.08  5364.4 1082.58  5399.1 1084.22  5421.2 1084.45
#Mann=5,-1,0
  4629.8    0.05       0  4988.6    0.03       0  5007.3    0.05       0
  5095.7    0.12       0  5364.4    0.05       0
Bank Sta=4988.6,5007.3
Exp/Cntr=0.3,0.1

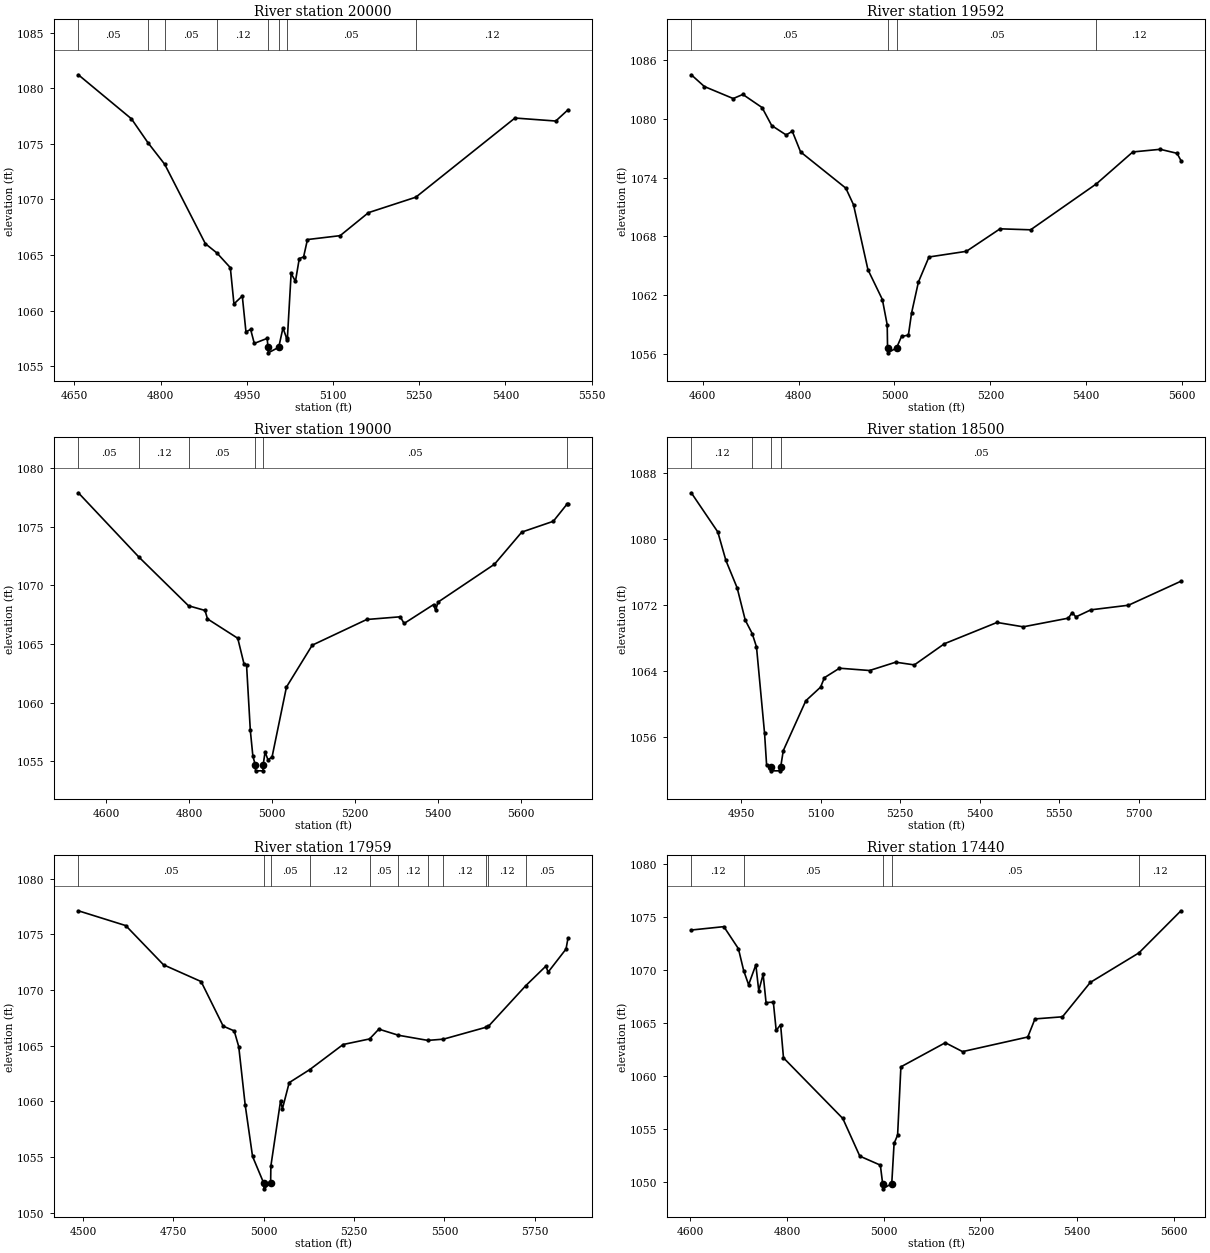
Type RM Length L Ch R = 1,20000,408,408,408
BEGIN DESCRIPTION:
FLAG CREEK 40.0
END DESCRIPTION:
XS GIS Cut Line= 3
      2808455.66     10232953.15      2808665.52     10232681.46
      2809005.69     10232303.10
#Sta/Elev= 30
  4656.7 1081.21  4749.1 1077.25  4777.7 1075.11  4807.0 1073.16  4877.7 1066.02
  4897.9 1065.18  4921.2 1063.86  4927.5 1060.60  4942.0 1061.31  4948.4 1058.08
  4956.5 1058.31  4962.9 1057.05  4985.3 1057.50  4986.7 1056.70  4987.2 1056.20
  5005.4 1056.70  5012.8 1058.44  5019.1 1057.52  5020.3 1057.34  5027.0 1063.35
  5034.5 1062.63  5041.2 1064.68  5048.7 1064.83  5055.4 1066.39  5112.3 1066.74
  5161.6 1068.81  5244.0 1070.20  5416.5 1077.32  5487.5 1077.05  5508.8 1078.06
#Mann=8,-1,0
  4656.7    0.05       0  4777.7    0.12       0  4807.0    0.05       0
  4897.9    0.12       0  4986.7    0.07       0  5005.4    0.12       0
  5019.1    0.05       0  5244.0    0.12       0
Bank Sta=4986.7,5005.4
Exp/Cntr=0.3,0.1

Type RM Length L Ch R = 1,19592,592,592,592
BEGIN DESCRIPTION:
FLAG CREEK 39.0
END DESCRIPTION:
XS GIS Cut Line= 3
      2808318.52     10233106.64      2808740.75     10233069.00
      2809125.83     10232611.88
#Sta/Elev= 30
  4576.1 1084.51  4603.4 1083.31  4663.6 1082.08  4683.7 1082.50  4723.8 1081.16
  4743.9 1079.32  4774.0 1078.36  4786.9 1078.73  4804.2 1076.62  4898.5 1072.92
  4914.6 1071.22  4944.7 1064.58  4974.8 1061.53  4984.9 1058.94  4985.6 1056.58
  4986.1 1056.08  5004.3 1056.58  5014.8 1057.76  5029.1 1057.89  5035.7 1060.15
  5050.0 1063.32  5072.0 1065.88  5150.1 1066.46  5220.3 1068.76  5284.1 1068.66
  5421.4 1073.36  5497.3 1076.62  5554.5 1076.89  5589.6 1076.48  5597.7 1075.74
#Mann=4,-1,0
  4576.1    0.05       0  4985.6    0.05       0  5004.3    0.05       0
  5421.4    0.12       0
Bank Sta=4985.6,5004.3
Exp/Cntr=0.3,0.1

Type RM Length L Ch R = 1,19000,500,500,500
BEGIN DESCRIPTION:
FLAG CREEK 38.0
END DESCRIPTION:
XS GIS Cut Line= 3
      2809455.70     10233803.14      2809206.07     10233408.82
      2809105.69     10232703.13
#Sta/Elev= 30
  4533.3 1077.89  4679.2 1072.41  4798.7 1068.26  4838.5 1067.86  4844.4 1067.14
  4917.3 1065.49  4932.6 1063.27  4938.5 1063.21  4947.6 1057.63  4953.7 1055.45
  4959.6 1054.69  4960.1 1054.19  4978.0 1054.19  4978.5 1054.69  4983.1 1055.80
  4990.2 1055.12  5000.0 1055.38  5034.6 1061.33  5096.7 1064.90  5228.0 1067.09
  5308.8 1067.32  5318.0 1066.75  5388.9 1068.36  5394.0 1067.87  5399.7 1068.57
  5535.7 1071.80  5601.5 1074.54  5677.4 1075.46  5710.6 1076.93  5712.8 1076.93
#Mann=6,-1,0
  4533.3    0.05       0  4679.2    0.12       0  4798.7    0.05       0
  4959.6    0.03       0  4978.5    0.05       0  5710.6    0.12       0
Bank Sta=4959.6,4978.5
Exp/Cntr=0.3,0.1

Type RM Length L Ch R = 1,18500,541,541,541
BEGIN DESCRIPTION:
FLAG CREEK 37.0
END DESCRIPTION:
XS GIS Cut Line= 3
      2809805.68     10233453.11      2809684.09     10233376.32
      2809155.69     10232803.12
#Sta/Elev= 30
  4856.2 1085.65  4906.2 1080.90  4921.5 1077.44  4942.7 1074.12  4958.0 1070.20
  4971.1 1068.57  4979.2 1066.95  4994.4 1056.48  4998.3 1052.58  5006.0 1052.42
  5006.5 1051.92  5024.4 1051.92  5024.9 1052.42  5029.7 1054.37  5072.2 1060.42
  5100.0 1062.07  5107.3 1063.22  5135.7 1064.37  5192.4 1064.09  5241.7 1065.10
  5276.9 1064.77  5333.6 1067.34  5432.8 1069.92  5482.2 1069.39  5567.2 1070.44
  5574.6 1071.12  5581.4 1070.59  5609.8 1071.45  5680.7 1072.01  5779.6 1074.92
#Mann=4,-1,0
  4856.2    0.12       0  4971.1    0.05       0  5006.0    0.03       0
  5024.9    0.05       0
Bank Sta=5006,5024.9
Exp/Cntr=0.3,0.1

Type RM Length L Ch R = 1,17959,519,519,519
BEGIN DESCRIPTION:
Mapping XS 0a95dfb3
END DESCRIPTION:
XS GIS Cut Line= 4
      2809980.90     10233293.24      2810024.30     10232954.72
      2809716.14     10232902.64      2809179.28     10232452.38
#Sta/Elev= 30
  4487.2 1077.11  4618.4 1075.78  4722.9 1072.26  4826.8 1070.76  4887.9 1066.76
  4918.4 1066.33  4930.9 1064.92  4948.8 1059.67  4969.1 1055.07  5000.2 1052.66
  5000.7 1052.16  5019.1 1052.66  5019.8 1054.21  5046.7 1060.08  5051.7 1059.34
  5070.5 1061.69  5127.4 1062.86  5219.6 1065.11  5292.8 1065.61  5318.5 1066.49
  5372.7 1065.94  5453.9 1065.48  5497.1 1065.59  5615.1 1066.66  5621.5 1066.74
  5724.3 1070.37  5780.4 1072.14  5786.9 1071.61  5836.3 1073.68  5841.7 1074.66
#Mann=11,-1,0
  4487.2    0.05       0  5000.2    0.03       0  5019.1    0.05       0
  5127.4    0.12       0  5292.8    0.05       0  5372.7    0.12       0
  5453.9    0.05       0  5497.1    0.12       0  5615.1    0.05       0
  5621.5    0.12       0  5724.3    0.05       0
Bank Sta=5000.2,5019.1
Exp/Cntr=0.3,0.1

Type RM Length L Ch R = 1,17440,360,360,360
BEGIN DESCRIPTION:
Mapping XS f4dc9e2d
END DESCRIPTION:
XS GIS Cut Line= 4
      2810015.62     10232737.72      2809846.35     10232481.63
      2809624.99     10232242.92      2809311.00     10232027.86
#Sta/Elev= 30
  4601.9 1073.79  4669.3 1074.11  4699.4 1072.03  4710.3 1069.96  4720.5 1068.62
  4735.5 1070.50  4741.5 1068.05  4750.6 1069.61  4756.6 1066.94  4771.7 1066.97
  4777.6 1064.30  4786.7 1064.84  4792.7 1061.71  4915.4 1055.98  4950.6 1052.42
  4993.1 1051.57  4997.8 1049.83  4998.3 1049.33  5016.7 1049.83  5021.5 1053.62
  5028.8 1054.41  5035.6 1060.86  5127.5 1063.14  5163.2 1062.30  5298.1 1063.68
  5313.0 1065.39  5369.9 1065.59  5427.5 1068.84  5528.1 1071.63  5615.0 1075.61
#Mann=5,-1,0
  4601.9    0.12       0  4710.3    0.05       0  4997.8    0.05       0
  5016.7    0.05       0  5528.1    0.12       0
Bank Sta=4997.8,5016.7
Exp/Cntr=0.3,0.1

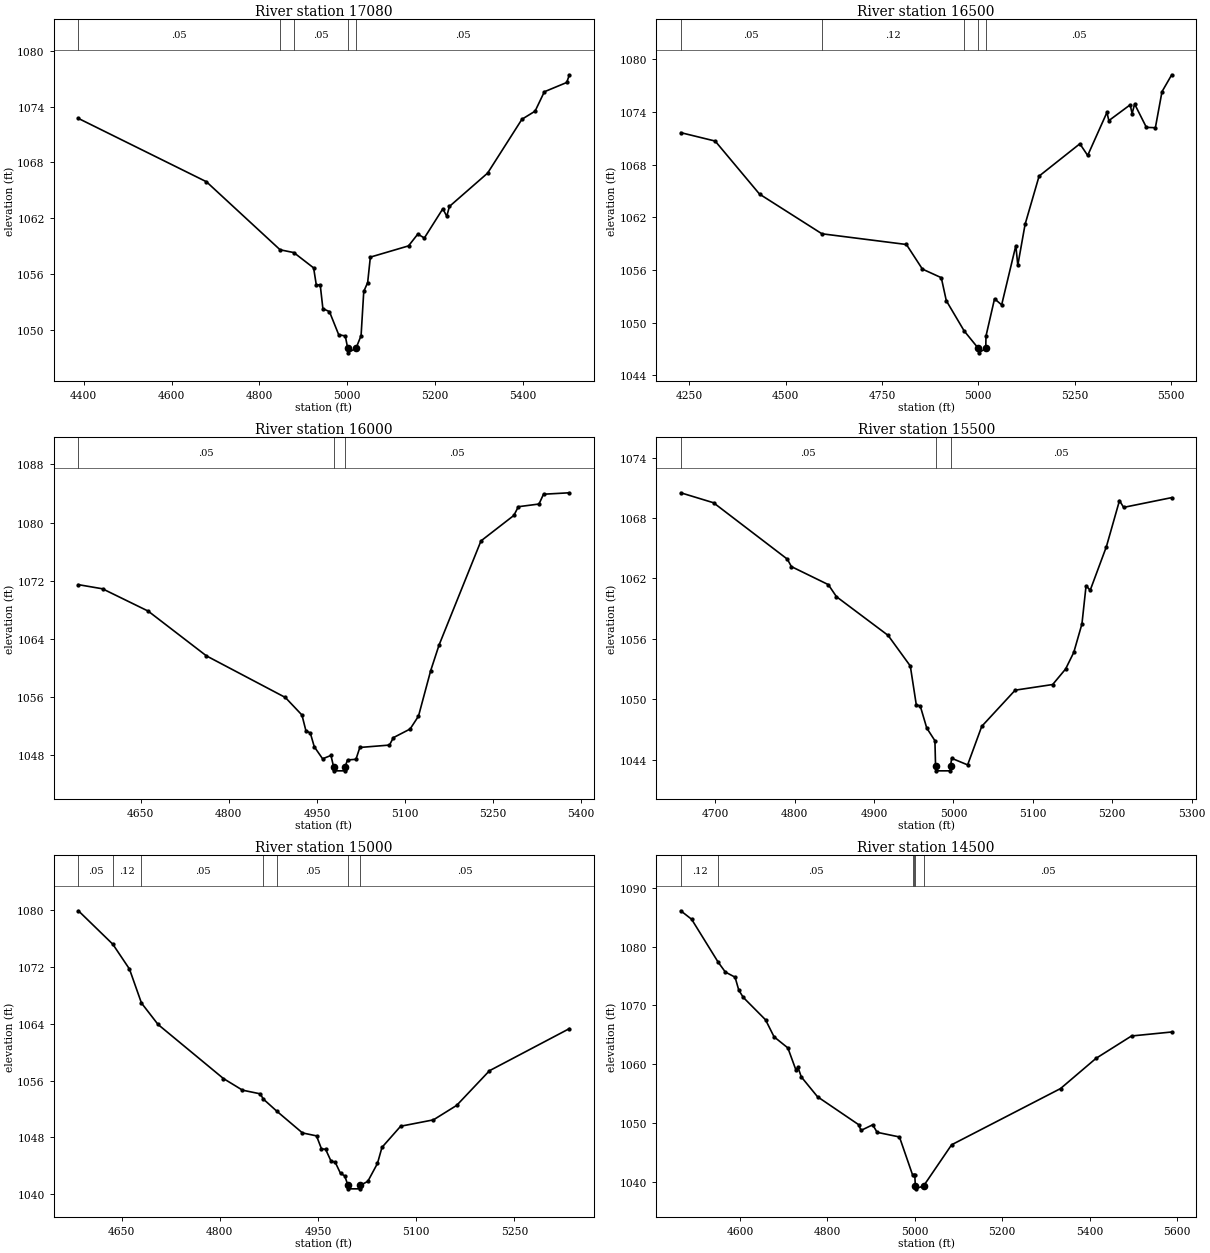
Type RM Length L Ch R = 1,17080,580,580,580
BEGIN DESCRIPTION:
Mapping XS a9b2b209
END DESCRIPTION:
XS GIS Cut Line= 3
      2810006.93     10232659.55      2809963.53     10232182.15
      2809607.61     10231652.62
#Sta/Elev= 30
  4388.1 1072.74  4679.4 1065.92  4847.1 1058.59  4878.3 1058.29  4923.4 1056.64
  4929.5 1054.80  4938.4 1054.82  4944.5 1052.25  4959.4 1051.93  4980.5 1049.44
  4995.4 1049.31  5001.0 1047.99  5001.5 1047.49  5019.9 1047.99  5031.4 1049.34
  5037.5 1054.10  5046.4 1055.06  5052.5 1057.80  5139.4 1059.01  5160.5 1060.28
  5175.4 1059.86  5217.5 1063.01  5226.4 1062.20  5232.5 1063.26  5319.4 1066.85
  5397.5 1072.65  5427.4 1073.52  5448.5 1075.61  5499.4 1076.61  5505.5 1077.44
#Mann=5,-1,0
  4388.1    0.05       0  4847.1    0.12       0  4878.3    0.05       0
  5001.0    0.05       0  5019.9    0.05       0
Bank Sta=5001,5019.9
Exp/Cntr=0.3,0.1

Type RM Length L Ch R = 1,16500,500,500,500
BEGIN DESCRIPTION:
FLAG CREEK 33.0
END DESCRIPTION:
XS GIS Cut Line= 3
      2810050.34     10232659.59      2810244.18     10231912.63
      2810328.11     10231418.30
#Sta/Elev= 30
  4228.3 1071.64  4317.6 1070.68  4432.6 1064.64  4594.4 1060.12  4813.5 1058.90
  4854.9 1056.10  4903.9 1055.12  4916.9 1052.50  4963.3 1049.05  5000.2 1047.06
  5000.7 1046.56  5019.2 1047.06  5019.8 1048.47  5042.0 1052.72  5060.4 1052.02
  5097.2 1058.77  5102.3 1056.54  5121.2 1061.20  5157.5 1066.69  5263.2 1070.37
  5283.5 1069.04  5333.4 1073.94  5338.4 1073.01  5393.7 1074.81  5398.7 1073.81
  5405.2 1074.90  5435.7 1072.24  5459.0 1072.20  5476.2 1076.31  5501.4 1078.23
#Mann=5,-1,0
  4228.3    0.05       0  4594.4    0.12       0  4963.3    0.05       0
  5000.2    0.03       0  5019.2    0.05       0
Bank Sta=5000.2,5019.2
Exp/Cntr=0.3,0.1

Type RM Length L Ch R = 1,16000,500,500,500
BEGIN DESCRIPTION:
FLAG CREEK 32.0
END DESCRIPTION:
XS GIS Cut Line= 3
      2810080.71     10232716.02      2810389.28     10232379.87
      2810636.30     10232090.98
#Sta/Elev= 30
  4543.7 1071.44  4584.8 1070.87  4662.5 1067.80  4761.8 1061.63  4896.2 1055.90
  4924.5 1053.48  4931.3 1051.30  4938.7 1051.01  4945.5 1049.11  4959.7 1047.45
  4973.9 1047.91  4978.6 1046.29  4979.1 1045.79  4997.1 1045.79  4997.6 1046.29
  5002.2 1047.29  5016.5 1047.38  5023.1 1049.01  5073.6 1049.34  5080.2 1050.36
  5108.7 1051.55  5123.0 1053.32  5143.8 1059.59  5158.1 1063.13  5229.5 1077.47
  5285.5 1080.98  5293.1 1082.18  5328.3 1082.55  5336.0 1083.90  5380.1 1084.10
#Mann=3,-1,0
  4543.7    0.05       0  4978.6    0.05       0  4997.6    0.05       0
Bank Sta=4978.6,4997.6
Exp/Cntr=0.3,0.1

Type RM Length L Ch R = 1,15500,500,500,500
BEGIN DESCRIPTION:
FLAG CREEK 31.0
END DESCRIPTION:
XS GIS Cut Line= 3
      2810155.72     10232953.10      2810488.34     10232866.90
      2810755.73     10232803.10
#Sta/Elev= 30
  4656.4 1070.50  4697.7 1069.51  4790.7 1063.91  4795.8 1063.17  4842.3 1061.38
  4852.6 1060.18  4917.6 1056.34  4945.6 1053.30  4953.1 1049.46  4958.2 1049.31
  4966.3 1047.14  4976.6 1045.88  4977.4 1043.39  4977.9 1042.89  4995.9 1042.89
  4996.4 1043.39  4997.6 1044.14  5017.8 1043.48  5035.6 1047.31  5077.7 1050.90
  5124.9 1051.46  5141.2 1053.00  5151.5 1054.65  5161.8 1057.48  5167.0 1061.27
  5172.2 1060.82  5192.6 1065.15  5209.1 1069.73  5214.3 1069.05  5274.9 1070.02
#Mann=3,-1,0
  4656.4    0.05       0  4977.4    0.03       0  4996.4    0.05       0
Bank Sta=4977.4,4996.4
Exp/Cntr=0.3,0.1

Type RM Length L Ch R = 1,15000,500,500,500
BEGIN DESCRIPTION:
FLAG CREEK 30.0
END DESCRIPTION:
XS GIS Cut Line= 3
      2810255.72     10233603.09      2810587.36     10233351.95
      2810855.71     10233153.09
#Sta/Elev= 30
  4584.0 1079.95  4636.6 1075.23  4662.0 1071.73  4680.3 1066.94  4705.7 1063.91
  4805.5 1056.29  4834.6 1054.65  4861.7 1054.13  4866.5 1053.39  4887.1 1051.68
  4926.2 1048.62  4947.7 1048.20  4955.3 1046.37  4961.6 1046.31  4969.9 1044.64
  4976.2 1044.50  4984.4 1042.90  4990.7 1042.57  4995.8 1041.23  4996.3 1040.73
  5014.3 1040.73  5014.8 1041.23  5026.1 1041.79  5040.8 1044.31  5047.7 1046.58
  5076.2 1049.56  5126.3 1050.46  5161.8 1052.50  5211.9 1057.39  5334.0 1063.33
#Mann=7,-1,0
  4584.0    0.05       0  4636.6    0.12       0  4680.3    0.05       0
  4866.5    0.12       0  4887.1    0.05       0  4995.8    0.05       0
  5014.8    0.05       0
Bank Sta=4995.8,5014.8
Exp/Cntr=0.3,0.1

Type RM Length L Ch R = 1,14500,500,500,500
BEGIN DESCRIPTION:
FLAG CREEK 29.0
END DESCRIPTION:
XS GIS Cut Line= 3
      2810355.68     10233853.11      2810880.12     10233742.38
      2811165.77     10233228.20
#Sta/Elev= 30
  4464.0 1086.08  4488.9 1084.64  4549.8 1077.33  4566.2 1075.66  4588.4 1074.79
  4596.9 1072.59  4607.1 1071.36  4658.2 1067.54  4677.7 1064.65  4709.3 1062.76
  4727.4 1059.08  4732.5 1059.46  4740.0 1057.84  4777.2 1054.46  4871.6 1049.70
  4876.7 1048.73  4903.5 1049.69  4913.7 1048.41  4964.8 1047.62  4995.1 1041.11
  4997.8 1041.09  5000.0 1041.09  5001.1 1039.30  5001.6 1038.80  5020.1 1039.30
  5084.2 1046.29  5333.6 1055.85  5414.9 1060.99  5496.1 1064.79  5588.2 1065.47
#Mann=6,-1,0
  4464.0    0.12       0  4549.8    0.05       0  4995.1    0.12       0
  4997.8    0.05       0  5001.1    0.05       0  5020.1    0.05       0
Bank Sta=5001.1,5020.1
Exp/Cntr=0.3,0.1

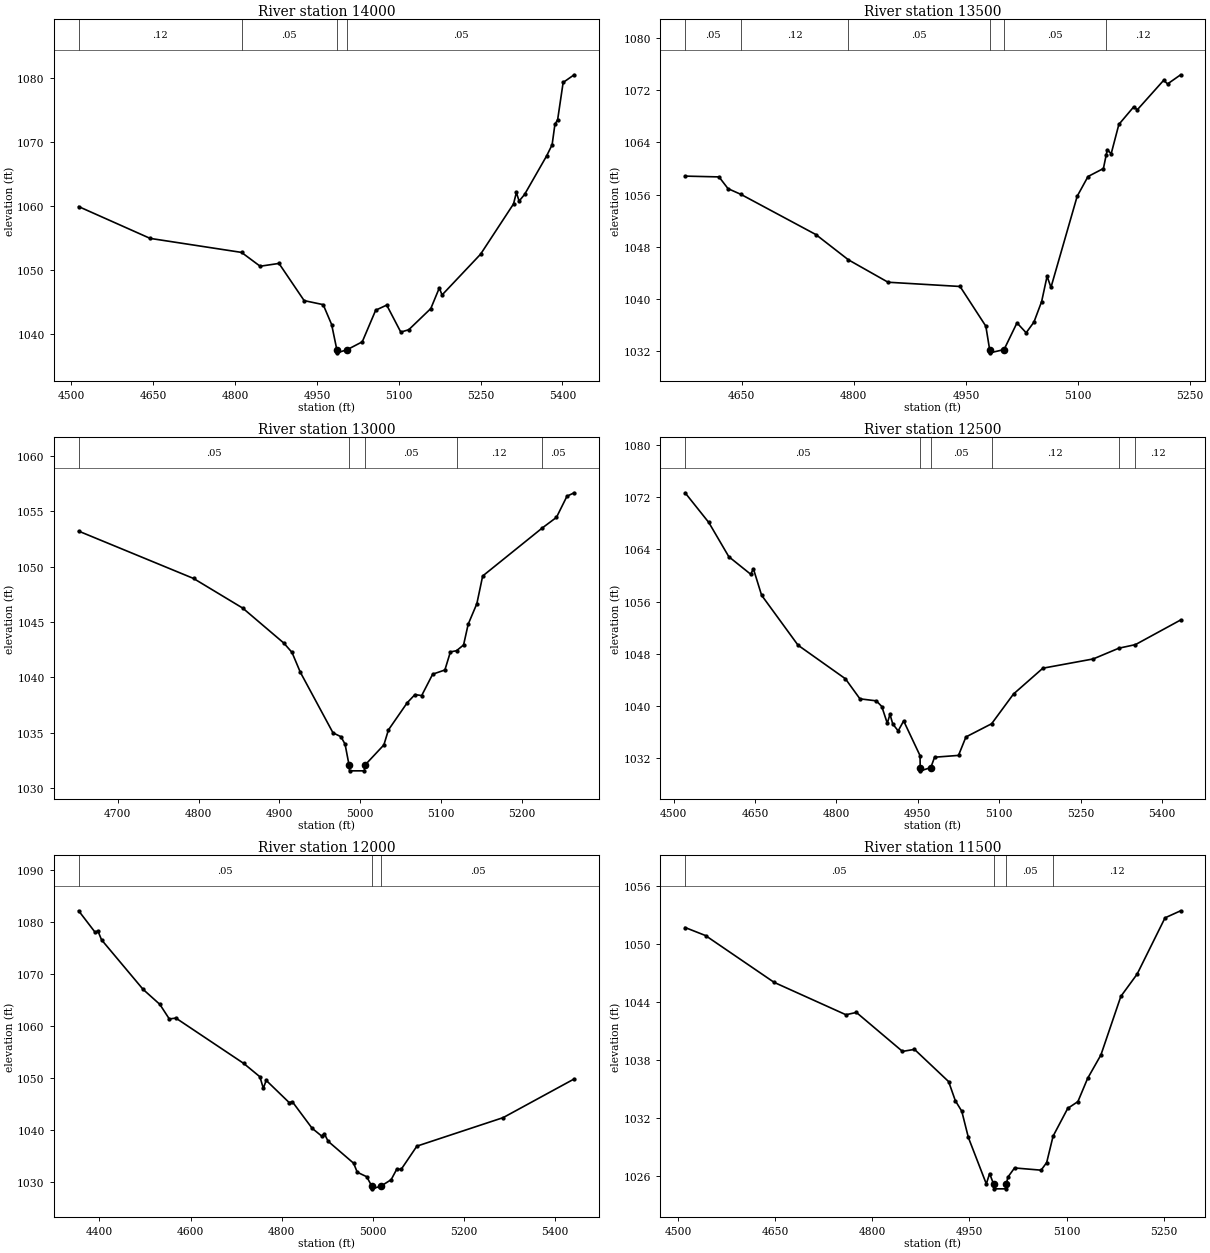
Type RM Length L Ch R = 1,14000,500,500,500
BEGIN DESCRIPTION:
FLAG CREEK 28.0
END DESCRIPTION:
XS GIS Cut Line= 3
      2810655.64     10234053.11      2811138.55     10234112.89
      2811555.69     10234053.11
#Sta/Elev= 30
  4513.4 1059.96  4644.4 1054.99  4811.9 1052.80  4846.0 1050.64  4880.5 1051.08
  4926.6 1045.27  4961.5 1044.64  4977.0 1041.53  4986.5 1037.61  4987.0 1037.11
  5005.6 1037.61  5033.1 1038.83  5057.7 1043.77  5077.9 1044.57  5103.7 1040.35
  5118.3 1040.72  5158.7 1044.03  5174.3 1047.25  5179.3 1046.15  5249.9 1052.52
  5310.3 1060.38  5315.5 1062.16  5320.5 1060.82  5330.5 1061.85  5370.9 1067.87
  5381.0 1069.62  5386.1 1072.80  5391.1 1073.53  5401.2 1079.35  5421.4 1080.55
#Mann=4,-1,0
  4513.4    0.12       0  4811.9    0.05       0  4986.5    0.05       0
  5005.6    0.05       0
Bank Sta=4986.5,5005.6
Exp/Cntr=0.3,0.1

Type RM Length L Ch R = 1,13500,500,500,500
BEGIN DESCRIPTION:
FLAG CREEK 27.0
END DESCRIPTION:
XS GIS Cut Line= 3
      2810955.71     10234303.12      2811325.97     10234513.59
      2811555.64     10234453.12
#Sta/Elev= 30
  4574.1 1058.82  4619.5 1058.70  4631.6 1056.90  4648.8 1056.03  4749.2 1049.88
  4792.7 1046.02  4845.8 1042.59  4942.2 1041.94  4976.7 1035.87  4981.8 1032.29
  4982.3 1031.79  5001.1 1032.29  5018.4 1036.37  5030.7 1034.86  5041.1 1036.49
  5051.4 1039.63  5058.7 1043.50  5063.9 1041.80  5099.0 1055.74  5113.5 1058.76
  5134.1 1059.98  5137.8 1062.03  5139.3 1062.86  5144.5 1062.24  5154.8 1066.73
  5174.5 1069.39  5179.6 1068.98  5214.8 1073.48  5220.0 1072.92  5237.5 1074.32
#Mann=6,-1,0
  4574.1    0.05       0  4648.8    0.12       0  4792.7    0.05       0
  4981.8    0.03       0  5001.1    0.05       0  5137.8    0.12       0
Bank Sta=4981.8,5001.1
Exp/Cntr=0.3,0.1

Type RM Length L Ch R = 1,13000,500,500,500
BEGIN DESCRIPTION:
FLAG CREEK 26.0
END DESCRIPTION:
XS GIS Cut Line= 3
      2810955.68     10234553.11      2811013.90     10234896.41
      2811255.70     10235003.12
#Sta/Elev= 30
  4651.8 1053.20  4793.8 1048.93  4854.7 1046.25  4905.4 1043.10  4915.5 1042.26
  4925.8 1040.47  4966.2 1035.00  4976.0 1034.65  4981.1 1033.98  4986.1 1032.07
  4986.6 1031.57  5005.0 1031.57  5005.5 1032.07  5029.1 1033.91  5034.7 1035.26
  5057.9 1037.71  5067.5 1038.45  5075.8 1038.36  5089.4 1040.29  5104.5 1040.67
  5111.3 1042.30  5118.9 1042.41  5127.6 1042.93  5133.3 1044.80  5144.0 1046.65
  5151.2 1049.15  5224.8 1053.48  5242.4 1054.44  5255.4 1056.35  5264.3 1056.66
#Mann=5,-1,0
  4651.8    0.05       0  4986.1    0.03       0  5005.5    0.05       0
  5118.9    0.12       0  5224.8    0.05       0
Bank Sta=4986.1,5005.5
Exp/Cntr=0.3,0.1

Type RM Length L Ch R = 1,12500,500,500,500
BEGIN DESCRIPTION:
FLAG CREEK 25.0
END DESCRIPTION:
XS GIS Cut Line= 3
      2810155.65     10235153.11      2810631.14     10235210.17
      2811055.68     10235303.11
#Sta/Elev= 30
  4521.1 1072.69  4564.8 1068.13  4601.7 1062.88  4642.0 1060.19  4647.0 1061.03
  4662.1 1056.97  4729.3 1049.30  4816.6 1044.15  4843.4 1041.07  4873.6 1040.76
  4883.7 1039.89  4893.8 1037.32  4898.8 1038.70  4903.9 1037.21  4913.9 1036.15
  4924.0 1037.68  4954.2 1032.35  4954.5 1030.52  4955.0 1030.02  4974.0 1030.52
  4981.0 1032.11  5025.1 1032.39  5038.8 1035.22  5086.2 1037.25  5126.5 1041.81
  5180.6 1045.77  5273.4 1047.19  5320.7 1048.84  5351.3 1049.39  5434.6 1053.17
#Mann=6,-1,0
  4521.1    0.05       0  4954.5    0.03       0  4974.0    0.05       0
  5086.2    0.12       0  5320.7    0.05       0  5351.3    0.12       0
Bank Sta=4954.5,4974
Exp/Cntr=0.3,0.1

Type RM Length L Ch R = 1,12000,500,500,500
BEGIN DESCRIPTION:
FLAG CREEK 24.0
END DESCRIPTION:
XS GIS Cut Line= 3
      2810105.72     10236053.08      2810608.60     10235648.07
      2811005.72     10235453.09
#Sta/Elev= 30
  4354.3 1082.15  4390.2 1078.04  4396.7 1078.24  4404.6 1076.56  4495.8 1067.02
  4532.6 1064.13  4553.4 1061.32  4567.8 1061.49  4716.6 1052.77  4752.3 1050.19
  4759.8 1047.97  4766.2 1049.49  4816.5 1045.23  4823.7 1045.37  4866.9 1040.28
  4887.7 1038.79  4894.1 1039.18  4902.1 1037.77  4958.1 1033.54  4966.1 1031.81
  4986.9 1030.94  4998.1 1029.11  4998.6 1028.61  5017.7 1029.11  5040.5 1030.37
  5052.5 1032.34  5063.0 1032.42  5097.0 1036.83  5286.4 1042.32  5442.4 1049.77
#Mann=3,-1,0
  4354.3    0.05       0  4998.1    0.05       0  5017.7    0.05       0
Bank Sta=4998.1,5017.7
Exp/Cntr=0.3,0.1

Type RM Length L Ch R = 1,11500,500,500,500
BEGIN DESCRIPTION:
FLAG CREEK 23.0
END DESCRIPTION:
XS GIS Cut Line= 3
      2810505.70     10236053.11      2810986.54     10235964.18
      2811255.70     10235903.11
#Sta/Elev= 30
  4511.0 1051.69  4542.5 1050.86  4648.4 1046.02  4759.3 1042.67  4775.4 1042.91
  4846.6 1038.88  4865.1 1039.09  4917.8 1035.76  4928.2 1033.78  4938.1 1032.70
  4948.3 1029.98  4976.0 1025.18  4981.1 1026.25  4987.2 1025.17  4987.7 1024.67
  5006.3 1024.67  5006.8 1025.17  5009.4 1025.89  5019.6 1026.83  5060.6 1026.60
  5069.2 1027.39  5079.1 1030.12  5101.7 1032.99  5117.4 1033.69  5132.4 1036.09
  5152.9 1038.51  5183.7 1044.57  5208.8 1046.87  5251.9 1052.69  5276.0 1053.42
#Mann=4,-1,0
  4511.0    0.05       0  4987.2    0.05       0  5006.8    0.05       0
  5079.1    0.12       0
Bank Sta=4987.2,5006.8
Exp/Cntr=0.3,0.1

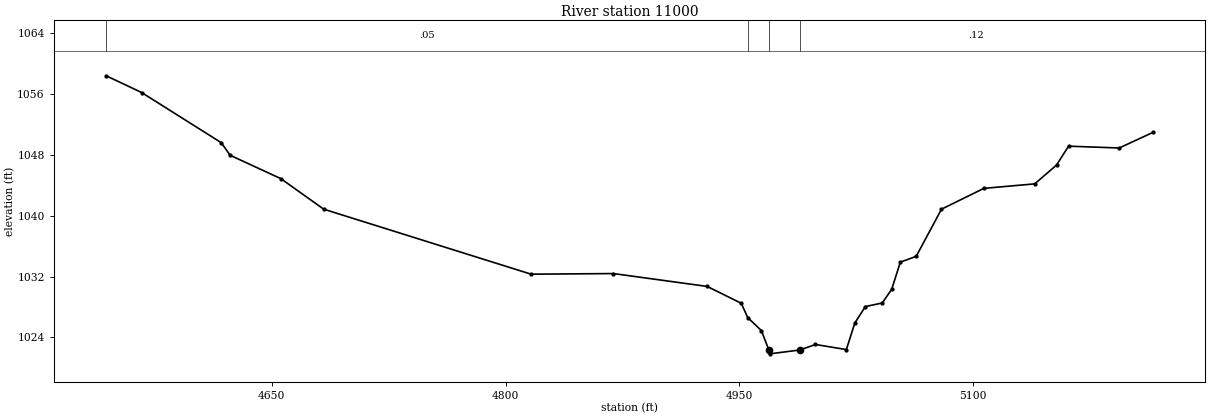
Type RM Length L Ch R = 1,11000,500,500,500
BEGIN DESCRIPTION:
FLAG CREEK 22.0
END DESCRIPTION:
XS GIS Cut Line= 3
      2811055.69     10236753.10      2811271.84     10236351.47
      2811355.67     10236153.16
#Sta/Elev= 30
  4543.9 1058.42  4566.6 1056.22  4617.7 1049.62  4623.4 1047.96  4655.9 1044.89
  4683.4 1040.87  4816.4 1032.32  4869.2 1032.40  4929.3 1030.71  4951.2 1028.49
  4955.3 1026.62  4964.1 1024.90  4968.9 1022.34  4969.4 1021.84  4988.6 1022.34
  4998.8 1023.07  5018.6 1022.40  5024.0 1025.89  5030.8 1028.06  5041.6 1028.53
  5047.7 1030.34  5053.2 1033.90  5063.4 1034.67  5079.6 1040.87  5106.8 1043.61
  5139.4 1044.20  5153.4 1046.68  5161.1 1049.16  5193.6 1048.92  5215.3 1050.98
#Mann=4,-1,0
  4543.9    0.05       0  4955.3    0.12       0  4968.9    0.07       0
  4988.6    0.12       0
Bank Sta=4968.9,4988.6
Exp/Cntr=0.3,0.1