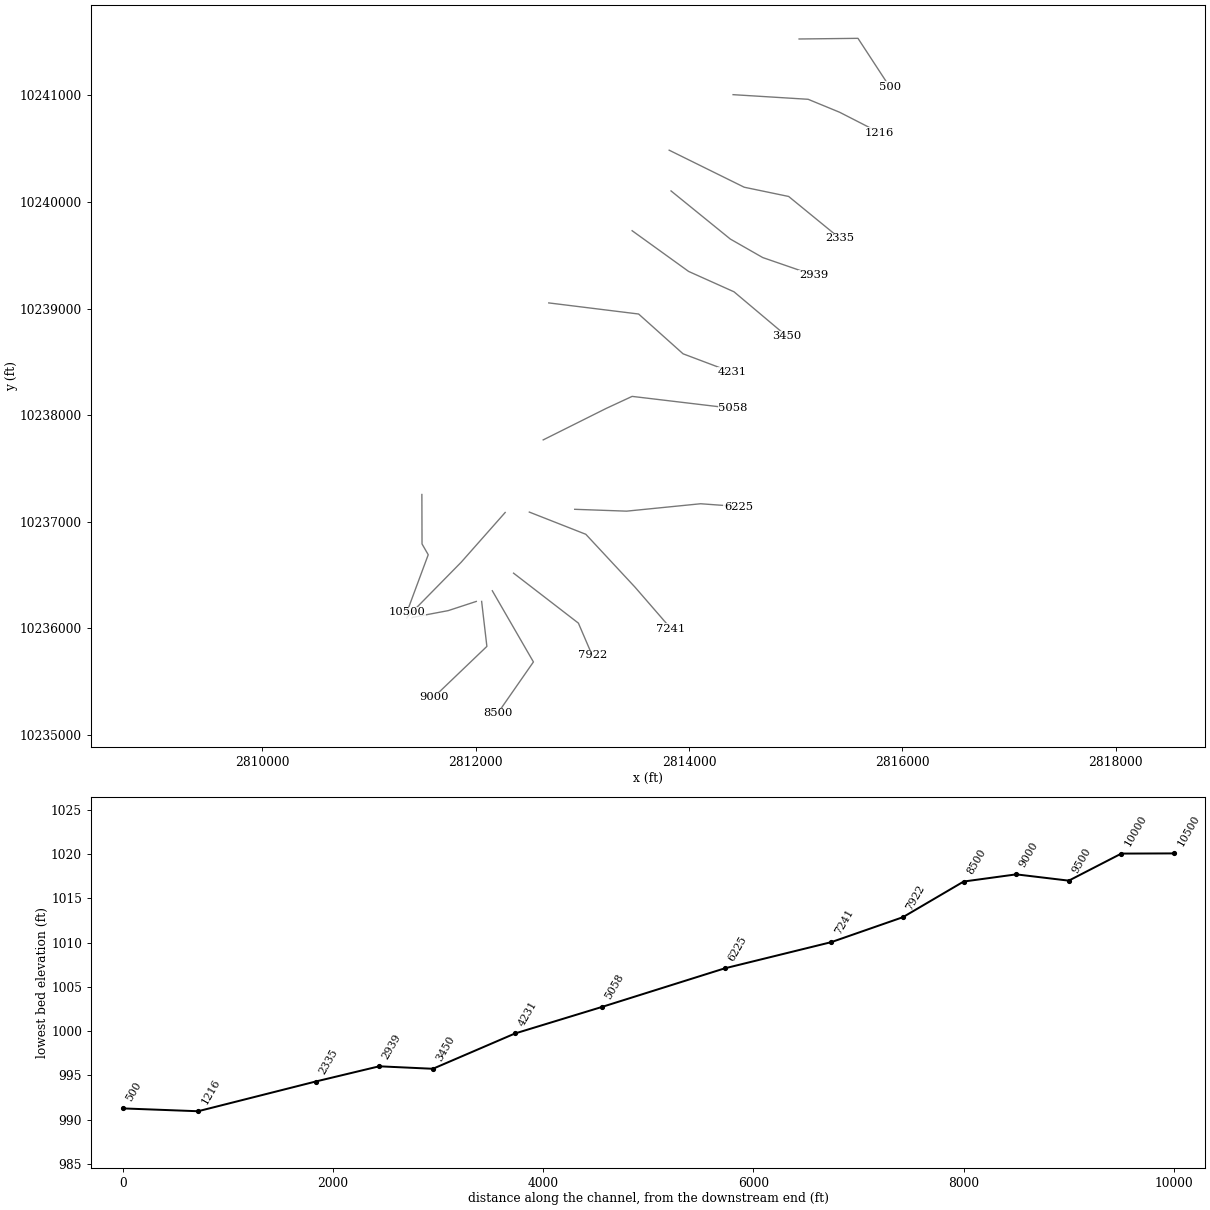
HEC-RAS study FLAG CREEK.prj: FLAG CREEK Base Level Engineering

--- FLAG CREEK.g01 (geometry) --- (continued)

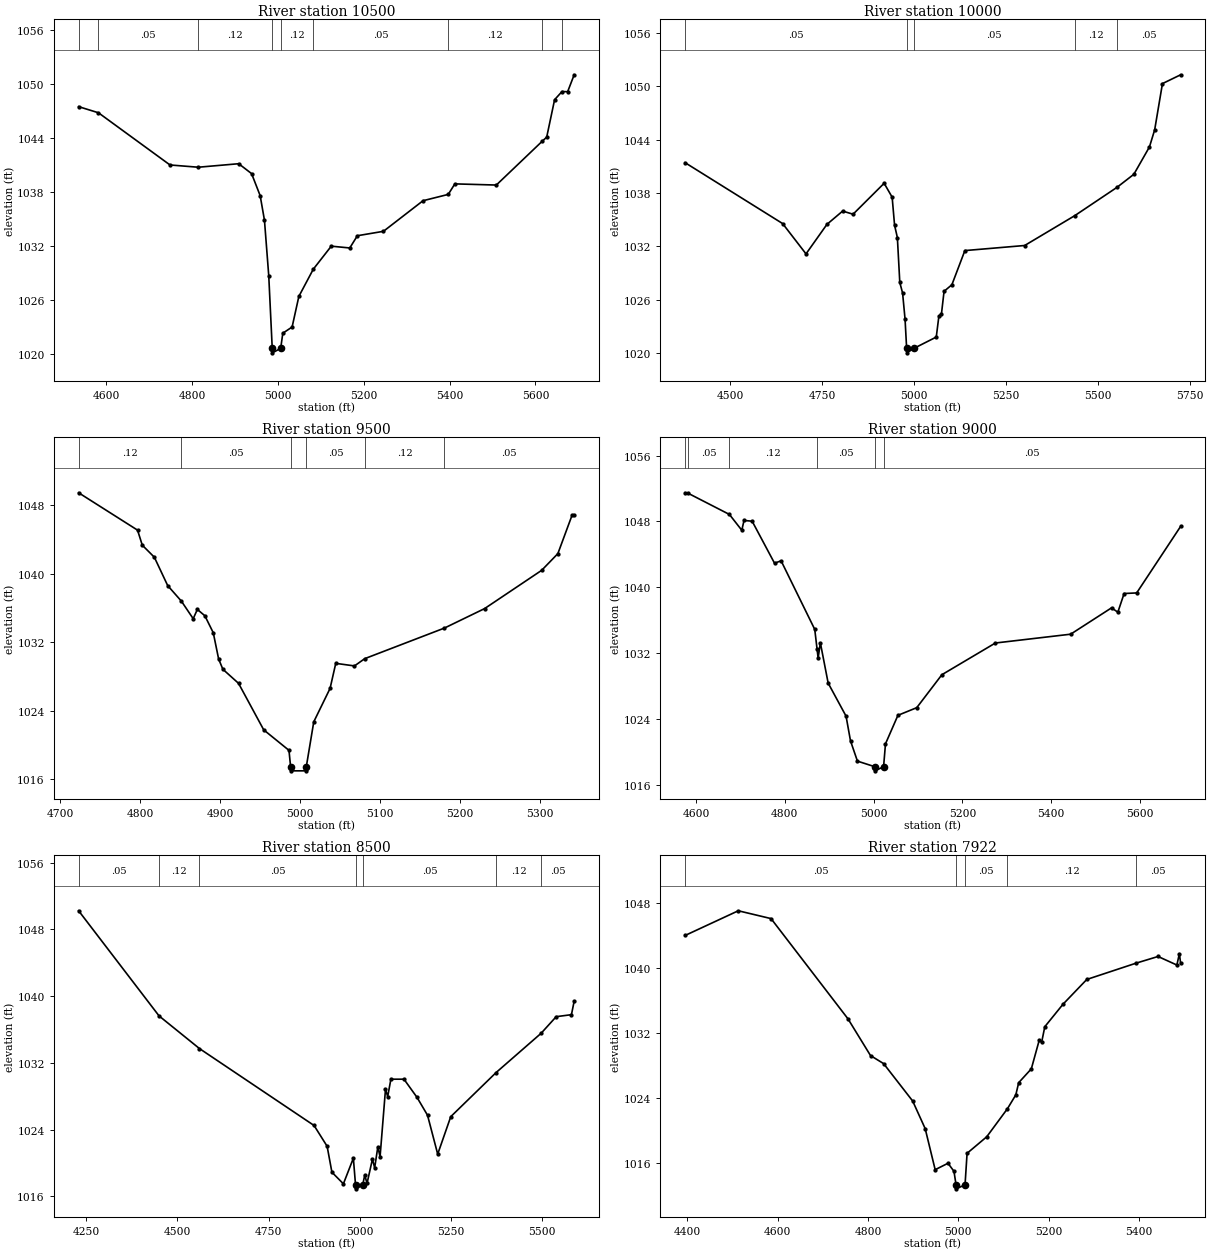
Type RM Length L Ch R = 1,10500,500,500,500
BEGIN DESCRIPTION:
FLAG CREEK 21.0
END DESCRIPTION:
XS GIS Cut Line= 4
      2811495.65     10237255.91      2811497.07     10236792.11
      2811555.18     10236690.99      2811355.69     10236153.12
#Sta/Elev= 30
  4536.2 1047.44  4582.3 1046.76  4749.0 1040.96  4814.9 1040.71  4909.0 1041.10
  4939.0 1040.00  4959.0 1037.55  4969.0 1034.82  4979.0 1028.64  4987.1 1020.59
  4987.6 1020.09  5006.8 1020.59  5011.7 1022.27  5033.4 1022.96  5049.1 1026.36
  5082.7 1029.38  5124.6 1031.94  5167.7 1031.74  5185.4 1033.10  5246.1 1033.59
  5338.3 1036.99  5397.0 1037.69  5412.4 1038.86  5509.0 1038.73  5616.4 1043.62
  5626.3 1044.05  5644.7 1048.21  5662.0 1049.12  5675.1 1049.10  5690.3 1050.98
#Mann=9,-1,0
  4536.2    0.12       0  4582.3    0.05       0  4814.9    0.12       0
  4987.1    0.07       0  5006.8    0.12       0  5082.7    0.05       0
  5397.0    0.12       0  5616.4    0.05       0  5662.0    0.12       0
Bank Sta=4987.1,5006.8
Exp/Cntr=0.3,0.1

Type RM Length L Ch R = 1,10000,500,500,500
BEGIN DESCRIPTION:
FLAG CREEK 20.0
END DESCRIPTION:
XS GIS Cut Line= 3
      2812276.26     10237087.09      2811864.04     10236620.64
      2811355.71     10236103.14
#Sta/Elev= 30
  4377.5 1041.40  4642.8 1034.57  4706.4 1031.17  4763.3 1034.48  4806.0 1035.97
  4834.4 1035.62  4918.9 1039.09  4940.7 1037.53  4947.3 1034.38  4954.9 1033.00
  4961.5 1027.96  4969.1 1026.78  4975.8 1023.85  4980.1 1020.57  4980.6 1020.07
  4999.8 1020.57  5060.7 1021.84  5067.7 1024.15  5074.9 1024.47  5081.9 1026.97
  5103.2 1027.71  5138.5 1031.54  5301.2 1032.11  5437.5 1035.46  5552.5 1038.64
  5598.2 1040.10  5640.6 1043.17  5654.8 1045.09  5675.9 1050.27  5725.4 1051.26
#Mann=5,-1,0
  4377.5    0.05       0  4980.1    0.03       0  4999.8    0.05       0
  5437.5    0.12       0  5552.5    0.05       0
Bank Sta=4980.1,4999.8
Exp/Cntr=0.3,0.1

Type RM Length L Ch R = 1,9500,500,500,500
BEGIN DESCRIPTION:
FLAG CREEK 19.0
END DESCRIPTION:
XS GIS Cut Line= 3
      2812005.69     10236253.11      2811742.39     10236166.78
      2811405.65     10236103.11
#Sta/Elev= 30
  4722.9 1049.45  4796.6 1045.09  4802.5 1043.34  4817.6 1041.93  4834.3 1038.62
  4851.4 1036.81  4866.2 1034.76  4871.4 1035.84  4880.8 1035.10  4891.3 1033.12
  4898.0 1030.06  4903.3 1028.86  4922.9 1027.22  4954.4 1021.79  4986.0 1019.40
  4988.0 1017.51  4988.5 1017.01  5007.2 1017.01  5007.7 1017.51  5017.0 1022.73
  5037.4 1026.63  5044.5 1029.55  5067.9 1029.25  5080.8 1030.10  5180.5 1033.67
  5230.7 1035.94  5302.0 1040.40  5322.3 1042.35  5340.1 1046.84  5342.7 1046.84
#Mann=6,-1,0
  4722.9    0.12       0  4851.4    0.05       0  4988.0    0.03       0
  5007.7    0.05       0  5080.8    0.12       0  5180.5    0.05       0
Bank Sta=4988,5007.7
Exp/Cntr=0.3,0.1

Type RM Length L Ch R = 1,9000,500,500,500
BEGIN DESCRIPTION:
FLAG CREEK 18.0
END DESCRIPTION:
XS GIS Cut Line= 3
      2812055.68     10236253.13      2812104.87     10235831.29
      2811605.66     10235353.08
#Sta/Elev= 30
  4575.3 1051.48  4582.5 1051.41  4675.1 1048.85  4703.0 1046.93  4708.0 1048.12
  4726.3 1048.03  4776.7 1042.93  4791.5 1043.22  4867.3 1034.89  4872.4 1032.55
  4874.9 1031.40  4879.9 1033.27  4897.5 1028.37  4937.8 1024.36  4947.8 1021.36
  4963.4 1018.90  5002.6 1018.22  5003.1 1017.72  5022.3 1018.22  5026.6 1021.00
  5054.6 1024.46  5097.0 1025.39  5153.6 1029.39  5274.1 1033.24  5443.6 1034.31
  5535.7 1037.51  5549.9 1036.98  5564.0 1039.25  5592.3 1039.32  5691.3 1047.40
#Mann=6,-1,0
  4575.3    0.12       0  4582.5    0.05       0  4675.1    0.12       0
  4872.4    0.05       0  5002.6    0.03       0  5022.3    0.05       0
Bank Sta=5002.6,5022.3
Exp/Cntr=0.3,0.1

Type RM Length L Ch R = 1,8500,578,578,578
BEGIN DESCRIPTION:
FLAG CREEK 17.0
END DESCRIPTION:
XS GIS Cut Line= 3
      2812155.71     10236353.07      2812541.09     10235685.53
      2812205.66     10235203.07
#Sta/Elev= 30
  4229.2 1050.23  4449.7 1037.63  4560.4 1033.72  4874.6 1024.50  4910.4 1022.01
  4923.5 1018.90  4955.0 1017.51  4982.3 1020.58  4988.2 1017.41  4988.7 1016.91
  5008.0 1017.41  5013.6 1018.57  5019.7 1017.55  5034.6 1020.47  5040.7 1019.42
  5049.4 1021.95  5055.5 1020.75  5070.4 1028.84  5076.4 1027.97  5085.2 1030.05
  5121.0 1030.05  5156.8 1027.87  5185.6 1025.73  5213.5 1021.07  5249.3 1025.56
  5373.7 1030.85  5497.0 1035.55  5538.3 1037.54  5580.1 1037.78  5587.6 1039.40
#Mann=7,-1,0
  4229.2    0.05       0  4449.7    0.12       0  4560.4    0.05       0
  4988.2    0.03       0  5008.0    0.05       0  5373.7    0.12       0
  5497.0    0.05       0
Bank Sta=4988.2,5008
Exp/Cntr=0.3,0.1

Type RM Length L Ch R = 1,7922,681,681,681
BEGIN DESCRIPTION:
Mapping XS 65c53565
END DESCRIPTION:
XS GIS Cut Line= 3
      2812355.04     10236518.08      2812962.66     10236049.34
      2813092.34     10235746.78
#Sta/Elev= 30
  4395.4 1043.98  4513.1 1047.01  4585.6 1046.05  4755.8 1033.75  4805.7 1029.24
  4834.7 1028.25  4899.0 1023.66  4926.7 1020.27  4948.8 1015.23  4977.2 1016.02
  4990.4 1015.03  4995.0 1013.38  4995.5 1012.88  5014.9 1013.38  5019.4 1017.24
  5062.9 1019.27  5108.8 1022.72  5127.3 1024.42  5133.6 1025.91  5161.6 1027.61
  5179.1 1031.13  5184.5 1030.89  5191.4 1032.78  5231.7 1035.54  5284.3 1038.58
  5393.4 1040.58  5442.0 1041.40  5483.7 1040.35  5489.2 1041.75  5492.0 1040.56
#Mann=5,-1,0
  4395.4    0.05       0  4995.0    0.05       0  5014.9    0.05       0
  5108.8    0.12       0  5393.4    0.05       0
Bank Sta=4995,5014.9
Exp/Cntr=0.3,0.1

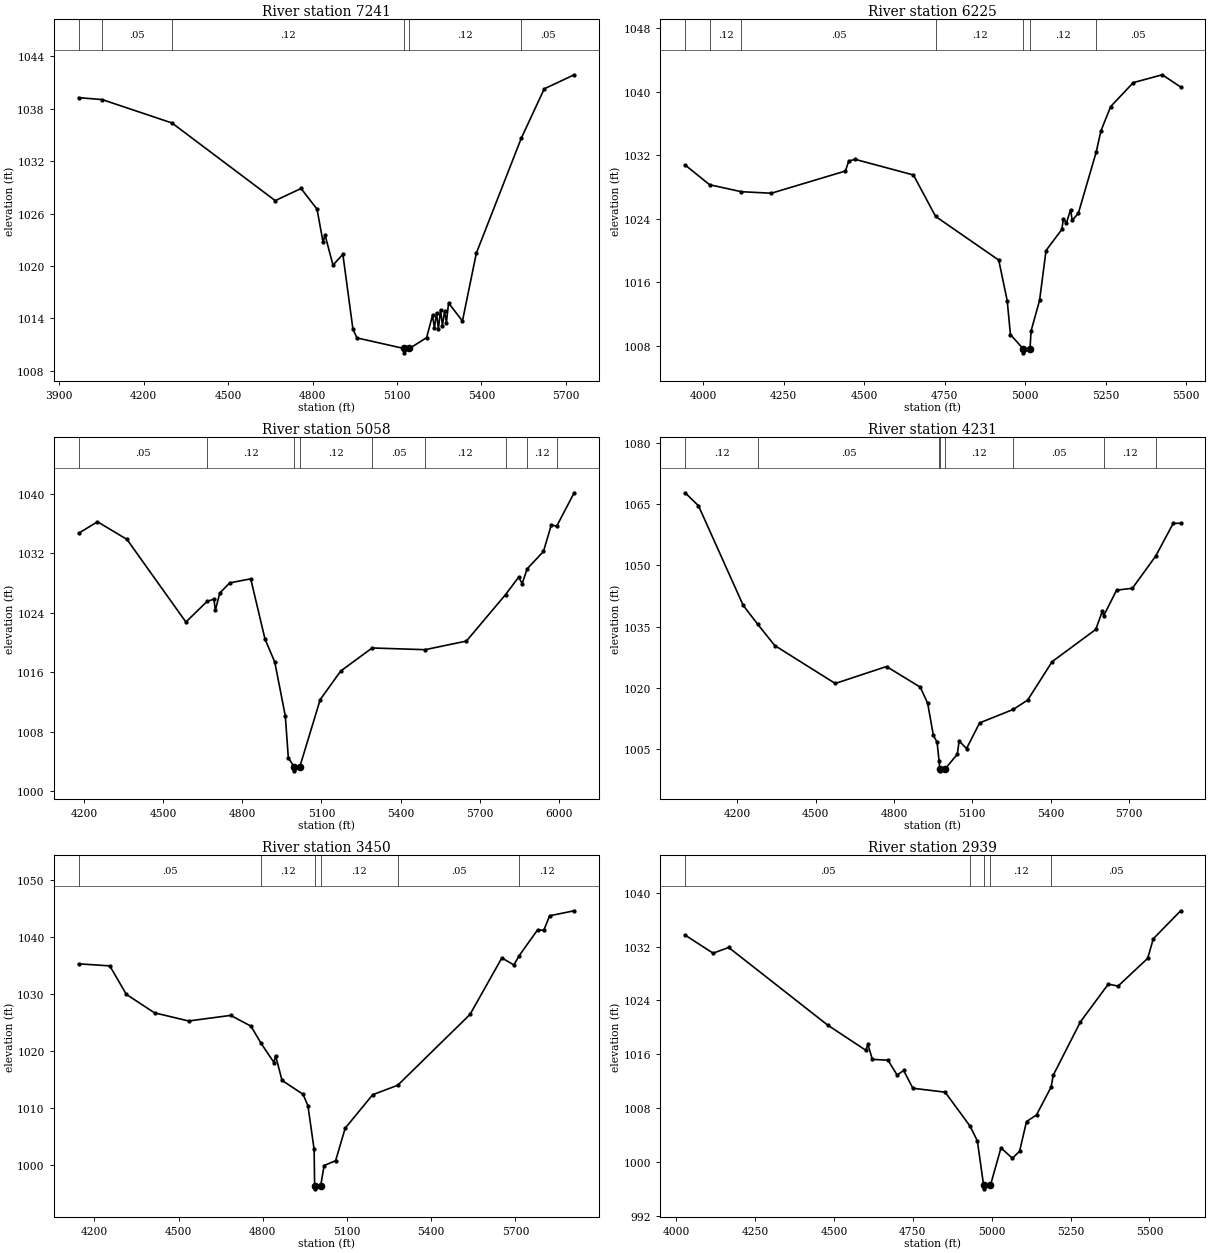
Type RM Length L Ch R = 1,7241,1016,1016,1016
BEGIN DESCRIPTION:
Mapping XS 0c400cc5
END DESCRIPTION:
XS GIS Cut Line= 4
      2812502.58     10237091.02      2813032.11     10236882.68
      2813492.18     10236387.88      2813830.34     10235997.70
#Sta/Elev= 30
  3968.5 1039.28  4052.1 1039.06  4300.3 1036.38  4667.1 1027.49  4759.0 1028.88
  4815.7 1026.51  4837.2 1022.72  4844.0 1023.57  4872.4 1020.11  4907.5 1021.34
  4943.2 1012.79  4957.4 1011.77  5124.3 1010.56  5124.8 1010.06  5144.2 1010.56
  5205.1 1011.80  5226.1 1014.35  5232.8 1012.89  5240.4 1014.65  5247.0 1012.78
  5254.6 1015.00  5261.3 1013.18  5268.9 1014.83  5275.5 1013.53  5283.1 1015.76
  5332.5 1013.71  5381.9 1021.48  5541.6 1034.64  5623.1 1040.29  5729.5 1041.90
#Mann=6,-1,0
  3968.5    0.12       0  4052.1    0.05       0  4300.3    0.12       0
  5124.3    0.07       0  5144.2    0.12       0  5541.6    0.05       0
Bank Sta=5124.3,5144.2
Exp/Cntr=0.3,0.1

Type RM Length L Ch R = 1,6225,1167,1167,1167
BEGIN DESCRIPTION:
Mapping XS 4d06fc2b
END DESCRIPTION:
XS GIS Cut Line= 4
      2812927.95     10237117.05      2813414.05     10237099.69
      2814108.50     10237169.13      2814462.53     10237143.23
#Sta/Elev= 30
  3944.0 1030.77  4020.1 1028.28  4119.1 1027.40  4211.9 1027.21  4442.1 1030.01
  4452.2 1031.26  4472.3 1031.48  4653.2 1029.51  4722.3 1024.28  4918.3 1018.78
  4944.6 1013.65  4954.6 1009.39  4994.5 1007.59  4995.0 1007.09  5015.3 1007.59
  5018.8 1009.86  5045.1 1013.70  5065.2 1019.99  5114.2 1022.64  5119.3 1024.01
  5128.3 1023.42  5141.4 1025.15  5146.5 1023.78  5165.6 1024.69  5220.7 1032.35
  5235.8 1035.08  5265.9 1038.13  5336.1 1041.15  5426.3 1042.14  5483.3 1040.60
#Mann=7,-1,0
  3944.0    0.05       0  4020.1    0.12       0  4119.1    0.05       0
  4722.3    0.12       0  4994.5    0.07       0  5015.3    0.12       0
  5220.7    0.05       0
Bank Sta=4994.5,5015.3
Exp/Cntr=0.3,0.1

Type RM Length L Ch R = 1,5058,827,827,827
BEGIN DESCRIPTION:
Mapping XS a98b01f6
END DESCRIPTION:
XS GIS Cut Line= 4
      2812632.78     10237768.08      2813223.08     10238063.23
      2813466.14     10238176.08      2814411.49     10238063.33
#Sta/Elev= 30
  4178.6 1034.69  4250.1 1036.24  4361.9 1033.87  4585.5 1022.75  4666.1 1025.53
  4691.8 1025.83  4697.3 1024.34  4714.1 1026.65  4752.0 1028.02  4831.5 1028.56
  4885.5 1020.48  4922.8 1017.35  4962.7 1010.11  4974.1 1004.50  4996.4 1003.23
  4996.9 1002.73  5017.3 1003.23  5095.0 1012.31  5172.7 1016.15  5292.1 1019.26
  5492.7 1019.03  5649.9 1020.19  5798.2 1026.44  5847.8 1028.78  5861.4 1027.93
  5880.4 1029.91  5942.0 1032.24  5972.2 1035.85  5991.9 1035.62  6058.6 1040.14
#Mann=9,-1,0
  4178.6    0.05       0  4666.1    0.12       0  4996.4    0.07       0
  5017.3    0.12       0  5292.1    0.05       0  5492.7    0.12       0
  5798.2    0.05       0  5880.4    0.12       0  5991.9    0.05       0
Bank Sta=4996.4,5017.3
Exp/Cntr=0.3,0.1

Type RM Length L Ch R = 1,4231,781,781,781
BEGIN DESCRIPTION:
Mapping XS 72fc397f
END DESCRIPTION:
XS GIS Cut Line= 4
      2812684.90     10239052.81      2813526.90     10238948.65
      2813943.57     10238575.38      2814402.18     10238402.32
#Sta/Elev= 30
  3999.8 1067.78  4051.0 1064.61  4222.3 1040.23  4278.6 1035.55  4343.2 1030.40
  4574.9 1021.11  4771.3 1025.26  4900.5 1020.21  4928.9 1016.27  4950.6 1008.44
  4964.8 1006.75  4972.6 1002.20  4975.2 1000.23  4975.7  999.73  4996.2 1000.23
  5042.6 1003.81  5049.3 1007.04  5077.7 1005.18  5127.8 1011.46  5256.7 1014.76
  5311.7 1017.04  5405.7 1026.45  5572.7 1034.33  5597.5 1038.74  5603.3 1037.72
  5652.6 1043.95  5713.0 1044.41  5802.6 1052.32  5869.5 1060.31  5897.8 1060.31
#Mann=8,-1,0
  3999.8    0.12       0  4278.6    0.05       0  4972.6    0.12       0
  4975.2    0.07       0  4996.2    0.12       0  5256.7    0.05       0
  5603.3    0.12       0  5802.6    0.05       0
Bank Sta=4975.2,4996.2
Exp/Cntr=0.3,0.1

Type RM Length L Ch R = 1,3450,511,511,511
BEGIN DESCRIPTION:
Mapping XS d9be6085
END DESCRIPTION:
XS GIS Cut Line= 4
      2813466.16     10239729.88      2813995.65     10239347.95
      2814421.00     10239156.98      2814915.81     10238740.29
#Sta/Elev= 30
  4143.5 1035.27  4254.6 1034.91  4313.4 1029.91  4414.0 1026.66  4535.5 1025.23
  4685.4 1026.21  4757.6 1024.32  4793.9 1021.29  4839.8 1017.92  4845.3 1019.15
  4868.4 1014.79  4943.4 1012.35  4960.8 1010.31  4982.7 1002.67  4984.6  996.24
  4985.1  995.74  5005.9  996.24  5018.4  999.84  5059.3 1000.68  5093.4 1006.39
  5191.5 1012.28  5280.5 1013.93  5538.5 1026.39  5651.7 1036.31  5694.6 1035.07
  5713.5 1036.70  5779.2 1041.24  5801.2 1041.16  5822.0 1043.71  5909.5 1044.59
#Mann=6,-1,0
  4143.5    0.05       0  4793.9    0.12       0  4984.6    0.07       0
  5005.9    0.12       0  5280.5    0.05       0  5713.5    0.12       0
Bank Sta=4984.6,5005.9
Exp/Cntr=0.3,0.1

Type RM Length L Ch R = 1,2939,604,604,604
BEGIN DESCRIPTION:
Mapping XS ef40b26b
END DESCRIPTION:
XS GIS Cut Line= 4
      2813830.75     10240103.14      2814386.28     10239651.77
      2814690.10     10239478.16      2815167.51     10239313.24
#Sta/Elev= 30
  4028.1 1033.71  4116.8 1031.02  4166.3 1031.87  4479.5 1020.36  4600.9 1016.60
  4607.4 1017.48  4621.8 1015.25  4671.3 1015.13  4700.1 1012.92  4720.9 1013.60
  4750.1 1010.96  4852.3 1010.38  4931.0 1005.36  4954.5 1003.15  4974.4  996.52
  4974.9  996.02  4995.8  996.52  5029.4 1002.10  5065.7 1000.56  5088.4 1001.61
  5110.3 1006.01  5142.0 1007.00  5188.4 1011.15  5194.9 1012.88  5281.3 1020.83
  5369.5 1026.42  5400.7 1026.14  5494.3 1030.25  5512.3 1033.16  5598.9 1037.32
#Mann=5,-1,0
  4028.1    0.05       0  4931.0    0.12       0  4974.4    0.07       0
  4995.8    0.12       0  5188.4    0.05       0
Bank Sta=4974.4,4995.8
Exp/Cntr=0.3,0.1

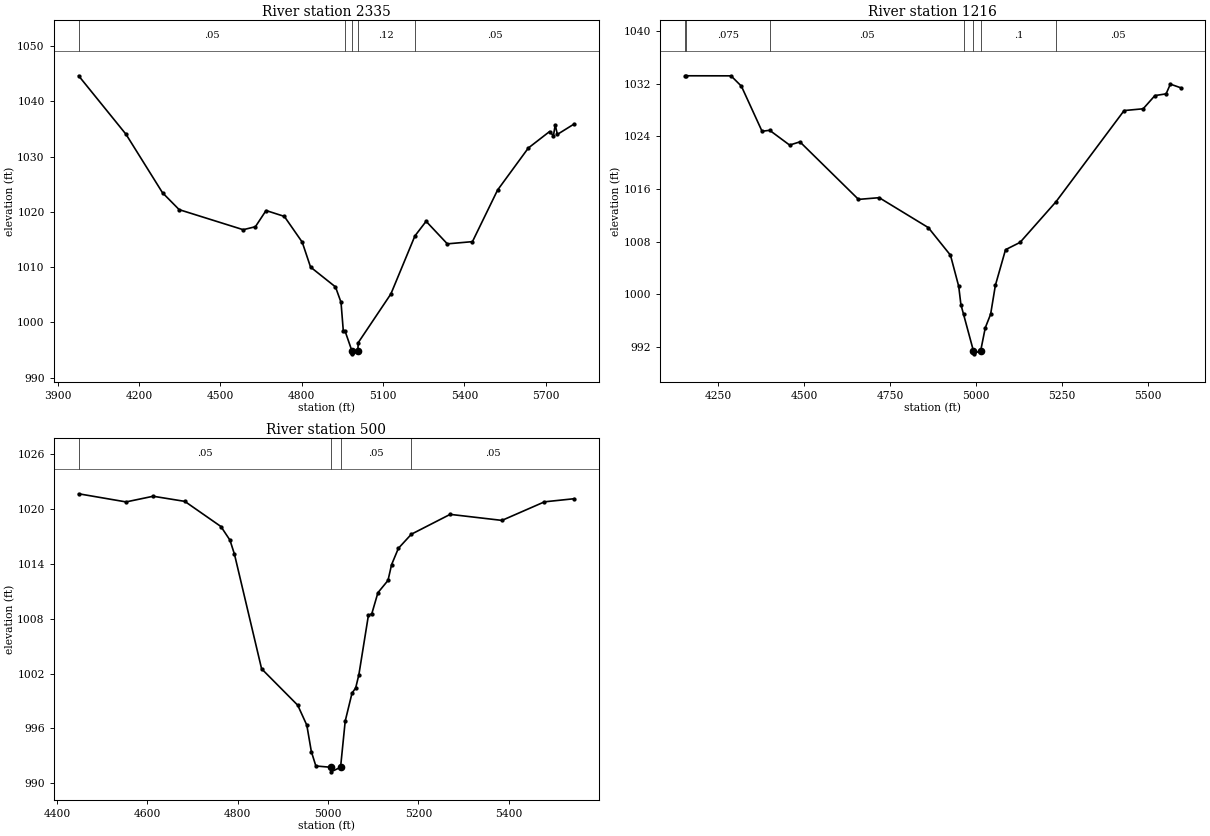
Type RM Length L Ch R = 1,2335,1119,1119,1119
BEGIN DESCRIPTION:
Mapping XS 46da5acd
END DESCRIPTION:
XS GIS Cut Line= 4
      2813813.36     10240485.10      2814516.48     10240137.88
      2814933.15     10240051.08      2815410.61     10239660.43
#Sta/Elev= 30
  3977.6 1044.61  4152.3 1034.02  4286.9 1023.44  4348.2 1020.39  4584.3 1016.76
  4629.2 1017.30  4668.5 1020.23  4735.8 1019.17  4801.8 1014.51  4832.5 1010.00
  4924.4 1006.41  4944.8 1003.63  4953.4  998.35  4959.8  998.41  4985.2  994.80
  4985.7  994.30  5006.6  994.80  5008.5  996.34  5128.7 1005.14  5217.2 1015.63
  5258.5 1018.28  5336.7 1014.20  5429.3 1014.60  5521.9 1023.93  5635.3 1031.54
  5713.6 1034.52  5727.9 1033.76  5734.4 1035.74  5742.3 1034.00  5804.3 1035.89
#Mann=5,-1,0
  3977.6    0.05       0  4959.8    0.12       0  4985.2    0.07       0
  5006.6    0.12       0  5217.2    0.05       0
Bank Sta=4985.2,5006.6
Exp/Cntr=0.3,0.1

Type RM Length L Ch R = 1,1216,716,716,716
BEGIN DESCRIPTION:
Mapping XS 252d919d
END DESCRIPTION:
XS GIS Cut Line= 4
      2814412.29     10241005.94      2815115.44     10240962.54
      2815410.58     10240841.01      2815782.29     10240650.83
#Sta/Elev= 30
  4153.2 1033.23  4156.8 1033.23  4286.8 1033.22  4316.9 1031.65  4377.0 1024.79
  4399.1 1024.94  4457.2 1022.69  4487.2 1023.18  4657.5 1014.43  4717.7 1014.69
  4860.5 1010.14  4925.0 1005.94  4949.0 1001.20  4955.3  998.44  4962.9  996.98
  4991.5  991.44  4992.0  990.94  5013.0  991.44  5026.2  994.90  5041.8  996.97
  5055.6 1001.36  5085.1 1006.78  5127.4 1007.89  5231.9 1014.07  5430.0 1027.94
  5485.4 1028.21  5519.6 1030.22  5552.1 1030.48  5564.5 1031.96  5594.4 1031.41
#Mann=7,-1,0
  4153.2    0.05       0  4156.8   0.075       0  4399.1    0.05       0
  4962.9     0.1       0  4991.5    0.07       0  5013.0     0.1       0
  5231.9    0.05       0
Bank Sta=4991.5,5013
Exp/Cntr=0.3,0.1

Type RM Length L Ch R = 1,500,0,0,0
BEGIN DESCRIPTION:
FLAG CREEK 1.0
END DESCRIPTION:
XS GIS Cut Line= 3
      2815030.67     10241528.11      2815582.73     10241534.23
      2815880.68     10241078.12
#Sta/Elev= 30
  4447.9 1021.65  4552.9 1020.76  4612.9 1021.38  4682.9 1020.82  4762.9 1018.07
  4782.9 1016.58  4792.9 1015.03  4852.9 1002.52  4932.9  998.54  4953.0  996.36
  4963.0  993.48  4973.0  991.90  5006.1  991.76  5006.6  991.26  5027.7  991.76
  5038.0  996.81  5053.1  999.87  5061.1 1000.42  5068.2 1001.87  5089.3 1008.35
  5096.9 1008.55  5110.4 1010.84  5132.7 1012.18  5140.6 1013.90  5155.7 1015.69
  5184.4 1017.23  5270.3 1019.40  5384.9 1018.74  5479.1 1020.77  5544.8 1021.11
#Mann=4,-1,0
  4447.9    0.05       0  5006.1    0.05       0  5027.7    0.05       0
  5184.4    0.05       0
Bank Sta=5006.1,5027.7
Exp/Cntr=0.3,0.1

Chan Stop Cuts=-1