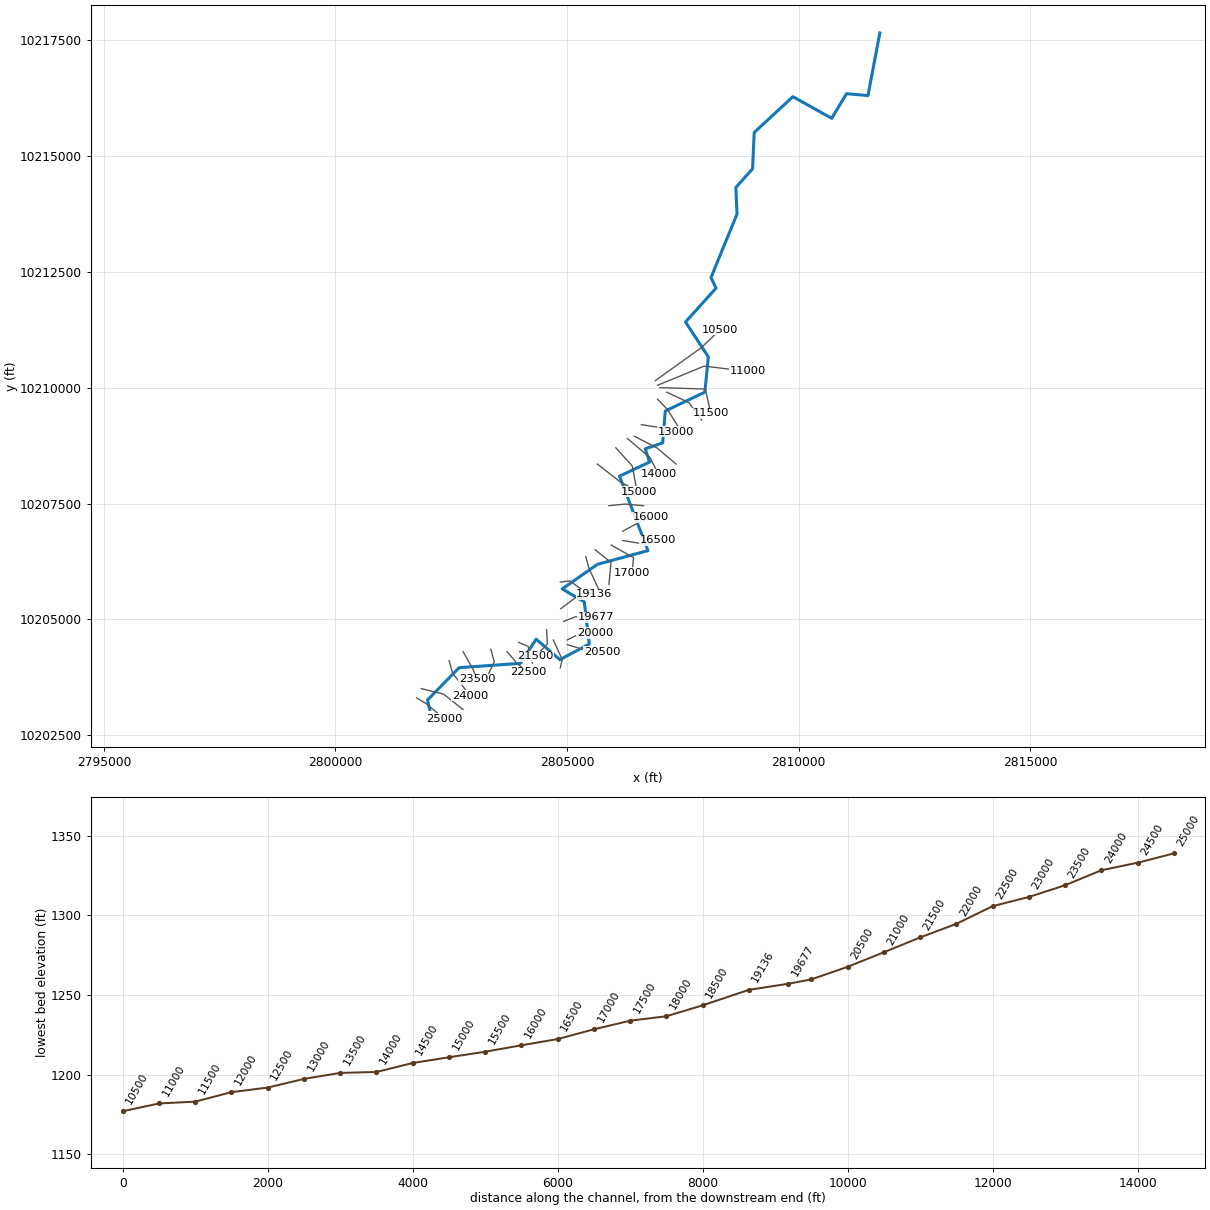
--- HICKORY MT BRANCH.prj (project) ---

Proj Title=HICKORY MT BRANCH Base Level Engineering
Current Plan=p01
Default Exp/Contr=0.3,0.1
English Units
Geom File=g01
Flow File=f01
Plan File=p01
BEGIN DESCRIPTION:
HICKORY MT BRANCH
END DESCRIPTION:

--- HICKORY MT BRANCH.p01 (plan) ---

Plan Title=Multiple Run
Short Identifier=Multiple
Geom File=g01
Flow File=f01
Subcritical Flow
K Sum by GR= 0
Std Step Tol= 0.01
Critical Tol= 0.01
Num of Std Step Trials= 20
Max Error Tol= 0.3
Flow Tol Ratio= 0.001
Split Flow NTrial= 30
Split Flow Tol= 0.02
Split Flow Ratio= 0.02
Log Output Level= 0
Friction Slope Method= 1
Unsteady Friction Slope Method= 2
Unsteady Bridges Friction Slope Method= 1
Parabolic Critical Depth
Global Vel Dist=  1 , 1 , 1
Global Log Level= 0
CheckData=True
Encroach Param= -1, 0, 0, 0
BEGIN DESCRIPTION:
Multiple Run
END DESCRIPTION:

--- HICKORY MT BRANCH.f01 (steady flow) ---

Flow Title=Multiple
Number of Profiles=7
Profile Names=10-year,25-year,50-year,1pct_min,100-year,1pct_plu,500-year
River Rch & RM= HICKORY MT BRANC,Reach-1,25000
     416     670    1160     697    1593    3640    2262
River Rch & RM= HICKORY MT BRANC,Reach-1,23500
     690    1161    1965    1277    2748    5912    3917
River Rch & RM= HICKORY MT BRANC,Reach-1,15500
     810    1376    2335    1496    3280    7188    4664
River Rch & RM= HICKORY MT BRANC,Reach-1,13000
     883    1510    2553    1650    3595    7835    5112
River Rch & RM= HICKORY MT BRANC,Reach-1,11000
    1203    2101    3511    2157    4984   11513    7055
River Rch & RM= HICKORY MT BRANC,Reach-1,4500
    1298    2272    3912    2298    5574   13523    7884
Boundary for River Rch & Prof#=HICKORY MT BRANC,Reach-1,1
Up Type=0
Dn Type=3
Dn Slope=0.005
Boundary for River Rch & Prof#=HICKORY MT BRANC,Reach-1,2
Up Type=0
Dn Type=3
Dn Slope=0.005
Boundary for River Rch & Prof#=HICKORY MT BRANC,Reach-1,3
Up Type=0
Dn Type=3
Dn Slope=0.005
Boundary for River Rch & Prof#=HICKORY MT BRANC,Reach-1,4
Up Type=0
Dn Type=3
Dn Slope=0.005
Boundary for River Rch & Prof#=HICKORY MT BRANC,Reach-1,5
Up Type=0
Dn Type=3
Dn Slope=0.005
Boundary for River Rch & Prof#=HICKORY MT BRANC,Reach-1,6
Up Type=0
Dn Type=3
Dn Slope=0.005
Boundary for River Rch & Prof#=HICKORY MT BRANC,Reach-1,7
Up Type=0
Dn Type=3
Dn Slope=0.005

--- HICKORY MT BRANCH.g01 (geometry) ---

Geom Title=Existing Conditions

River Reach=HICKORY MT BRANC,Reach-1
Reach XY= 30
      2802036.25     10203054.00      2801988.25     10203258.00
      2802671.50     10203956.00      2803994.00     10204049.00
      2804334.25     10204571.00      2804848.00     10204129.00
      2805481.00     10204466.00      2805374.00     10205377.00
      2804897.00     10205656.00      2805657.50     10206187.00
      2806749.25     10206484.00      2806133.75     10208091.00
      2806785.50     10208396.00      2806689.00     10208681.00
      2807065.75     10208808.00      2807122.75     10209498.00
      2807977.00     10209905.00      2808052.00     10210668.00
      2807559.25     10211420.00      2808218.50     10212150.00
      2808109.50     10212379.00      2808672.00     10213751.00
      2808646.00     10214325.00      2809007.75     10214728.00
      2809042.75     10215512.00      2809878.50     10216285.00
      2810716.00     10215818.00      2811036.25     10216350.00
      2811499.00     10216309.00      2811756.00     10217661.00

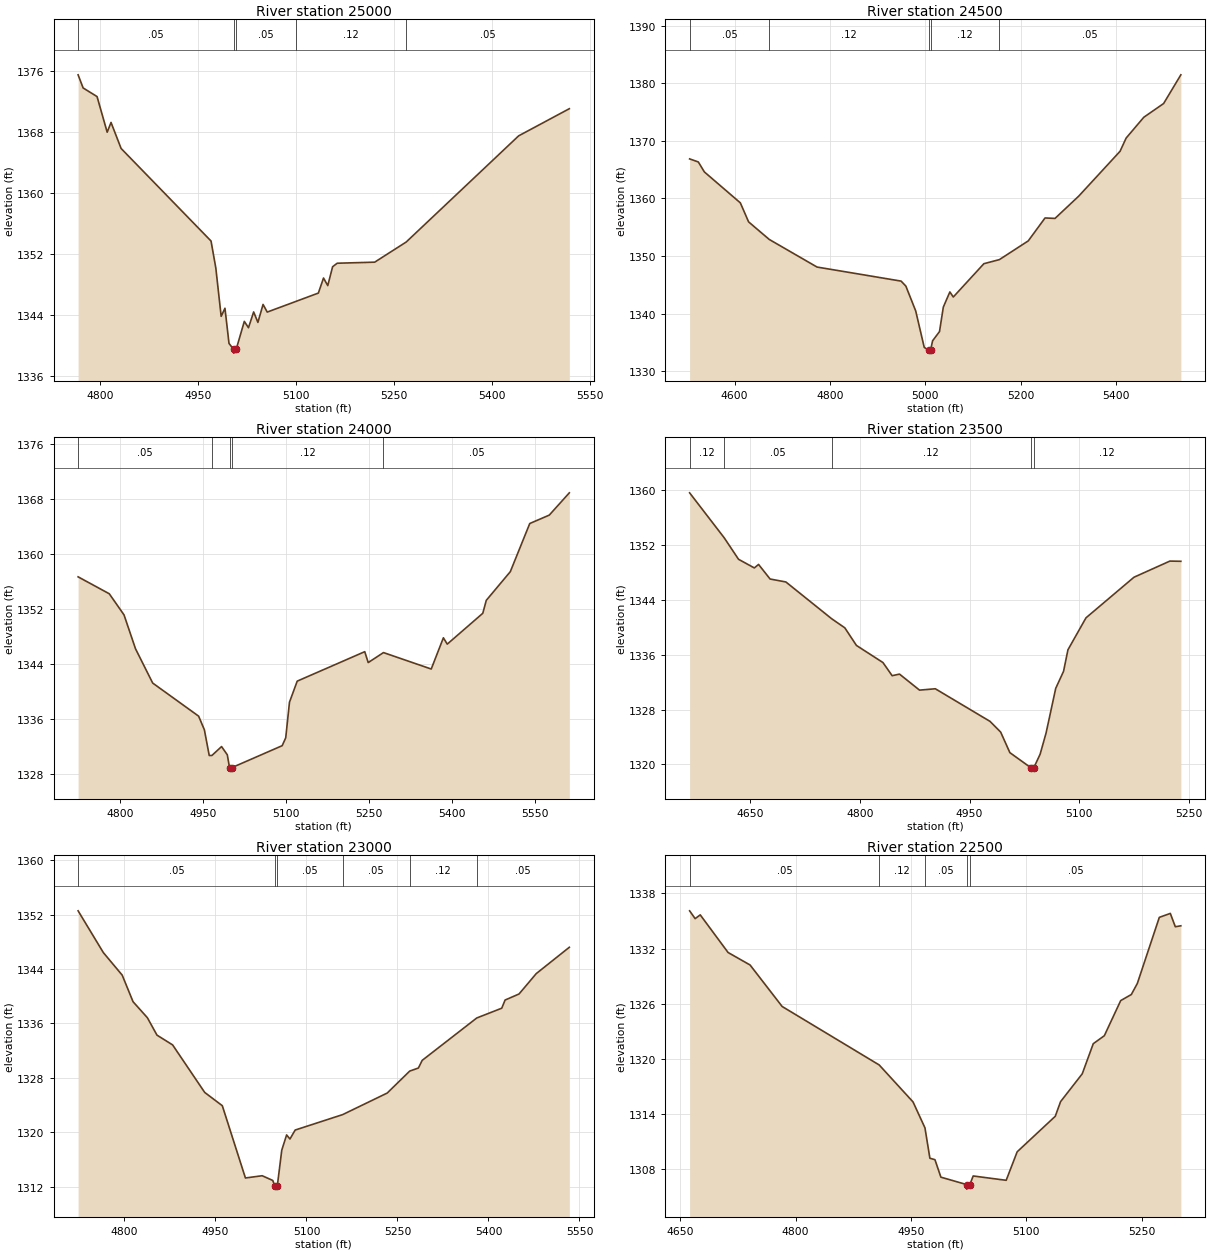
Type RM Length L Ch R = 1,25000,500,500,500
BEGIN DESCRIPTION:
HICKORY MT BRANCH 50.0
END DESCRIPTION:
XS GIS Cut Line= 3
      2801755.70     10203303.10      2801955.24     10203181.65
      2802355.71     10202853.09
#Sta/Elev= 30
  4766.4 1375.46  4774.1 1373.74  4795.4 1372.61  4810.9 1367.94  4816.8 1369.22
  4832.2 1365.81  4969.8 1353.68  4977.1 1350.16  4985.3 1343.81  4991.1 1344.87
  4997.3 1340.26  5004.3 1339.49  5004.6 1338.99  5008.3 1339.49  5020.7 1343.15
  5027.1 1342.32  5035.0 1344.39  5041.5 1343.02  5049.4 1345.37  5055.8 1344.37
  5100.1 1345.78  5134.0 1346.86  5141.9 1348.83  5148.4 1347.84  5155.8 1350.31
  5162.8 1350.77  5220.2 1350.91  5268.4 1353.55  5440.4 1367.46  5518.0 1371.02
#Mann=5,-1,0
  4766.4    0.05       0  5004.3    0.05       0  5008.3    0.05       0
  5100.1    0.12       0  5268.4    0.05       0
Bank Sta=5004.3,5008.3
Exp/Cntr=0.3,0.1

Type RM Length L Ch R = 1,24500,500,500,500
BEGIN DESCRIPTION:
HICKORY MT BRANCH 49.0
END DESCRIPTION:
XS GIS Cut Line= 3
      2801855.68     10203503.11      2802335.50     10203384.75
      2802755.69     10203053.11
#Sta/Elev= 30
  4505.8 1366.85  4524.0 1366.32  4536.7 1364.59  4612.1 1359.22  4629.4 1355.92
  4672.7 1352.87  4772.8 1348.08  4949.0 1345.64  4959.0 1344.77  4979.6 1340.47
  4997.5 1334.14  5006.7 1333.64  5006.9 1333.14  5010.7 1333.64  5015.0 1335.28
  5029.5 1336.88  5037.5 1341.13  5051.2 1343.76  5058.4 1342.88  5122.5 1348.66
  5155.0 1349.37  5215.5 1352.62  5250.7 1356.60  5271.6 1356.52  5321.2 1360.38
  5407.9 1368.17  5420.6 1370.46  5457.6 1374.07  5499.2 1376.46  5535.3 1381.44
#Mann=5,-1,0
  4505.8    0.05       0  4672.7    0.12       0  5006.7    0.07       0
  5010.7    0.12       0  5155.0    0.05       0
Bank Sta=5006.7,5010.7
Exp/Cntr=0.3,0.1

Type RM Length L Ch R = 1,24000,500,500,500
BEGIN DESCRIPTION:
HICKORY MT BRANCH 48.0
END DESCRIPTION:
XS GIS Cut Line= 3
      2802455.68     10204103.12      2802530.31     10203836.67
      2802905.71     10203353.08
#Sta/Elev= 30
  4723.3 1356.64  4779.7 1354.18  4806.4 1351.11  4827.2 1346.18  4858.3 1341.20
  4941.4 1336.39  4951.8 1334.41  4960.6 1330.67  4965.5 1330.68  4982.9 1331.97
  4993.3 1330.77  4997.3 1328.90  4997.5 1328.40  5001.3 1328.90  5092.6 1332.10
  5099.0 1333.24  5105.8 1338.42  5119.8 1341.48  5242.0 1345.76  5248.3 1344.18
  5275.9 1345.63  5362.3 1343.24  5384.3 1347.78  5391.3 1346.86  5455.6 1351.34
  5461.9 1353.22  5505.4 1357.39  5540.6 1364.39  5575.9 1365.61  5612.2 1368.85
#Mann=5,-1,0
  4723.3    0.05       0  4965.5    0.12       0  4997.3    0.07       0
  5001.3    0.12       0  5275.9    0.05       0
Bank Sta=4997.3,5001.3
Exp/Cntr=0.3,0.1

Type RM Length L Ch R = 1,23500,500,500,500
BEGIN DESCRIPTION:
HICKORY MT BRANCH 47.0
END DESCRIPTION:
XS GIS Cut Line= 3
      2802755.68     10204303.13      2802970.21     10203926.66
      2803055.67     10203703.14
#Sta/Elev= 30
  4566.7 1359.66  4614.0 1353.10  4633.7 1349.95  4655.3 1348.69  4661.1 1349.20
  4676.9 1347.07  4698.5 1346.64  4761.3 1341.26  4779.2 1339.94  4795.1 1337.37
  4831.4 1334.87  4844.0 1332.95  4854.1 1333.18  4881.5 1330.84  4903.1 1331.04
  4978.0 1326.28  4992.6 1324.71  5005.2 1321.71  5033.9 1319.51  5034.2 1319.01
  5038.0 1319.51  5046.6 1321.48  5054.7 1324.55  5068.0 1331.11  5078.7 1333.59
  5084.7 1336.73  5109.4 1341.40  5175.1 1347.33  5224.3 1349.69  5239.3 1349.66
#Mann=5,-1,0
  4566.7    0.12       0  4614.0    0.05       0  4761.3    0.12       0
  5033.9    0.07       0  5038.0    0.12       0
Bank Sta=5033.9,5038
Exp/Cntr=0.3,0.1

Type RM Length L Ch R = 1,23000,500,500,500
BEGIN DESCRIPTION:
HICKORY MT BRANCH 46.0
END DESCRIPTION:
XS GIS Cut Line= 3
      2803355.68     10204353.14      2803430.01     10204086.93
      2803205.68     10203603.10
#Sta/Elev= 30
  4723.6 1352.56  4765.2 1346.42  4796.3 1343.10  4814.2 1339.19  4837.8 1336.84
  4853.6 1334.28  4879.4 1332.84  4932.3 1325.85  4961.3 1323.90  4999.4 1313.27
  5027.0 1313.60  5044.4 1312.91  5047.8 1312.13  5048.1 1311.63  5052.0 1312.13
  5059.3 1317.36  5067.3 1319.60  5072.8 1319.00  5081.4 1320.32  5159.7 1322.59
  5233.1 1325.76  5270.2 1328.99  5284.5 1329.44  5290.8 1330.57  5380.7 1336.80
  5421.9 1338.24  5427.4 1339.44  5450.4 1340.33  5478.8 1343.33  5533.3 1347.20
#Mann=6,-1,0
  4723.6    0.05       0  5047.8    0.05       0  5052.0    0.05       0
  5159.7    0.05       0  5270.2    0.12       0  5380.7    0.05       0
Bank Sta=5047.8,5052
Exp/Cntr=0.3,0.1

Type RM Length L Ch R = 1,22500,500,500,500
BEGIN DESCRIPTION:
HICKORY MT BRANCH 45.0
END DESCRIPTION:
XS GIS Cut Line= 3
      2803705.65     10204303.15      2803924.86     10204046.00
      2804155.68     10203853.12
#Sta/Elev= 30
  4662.1 1336.11  4669.3 1335.26  4675.9 1335.67  4712.1 1331.58  4740.7 1330.22
  4782.4 1325.71  4908.6 1319.35  4952.6 1315.33  4968.1 1312.51  4974.5 1309.21
  4981.1 1309.05  4988.8 1307.15  5022.1 1306.35  5022.4 1305.85  5026.5 1306.35
  5030.8 1307.28  5073.7 1306.81  5088.0 1309.91  5137.5 1313.77  5144.4 1315.36
  5172.6 1318.39  5186.9 1321.66  5201.3 1322.53  5222.6 1326.35  5236.4 1327.01
  5244.2 1328.21  5272.8 1335.40  5287.1 1335.83  5293.6 1334.38  5300.8 1334.48
#Mann=5,-1,0
  4662.1    0.05       0  4908.6    0.12       0  4968.1    0.05       0
  5022.1    0.05       0  5026.5    0.05       0
Bank Sta=5022.1,5026.5
Exp/Cntr=0.3,0.1

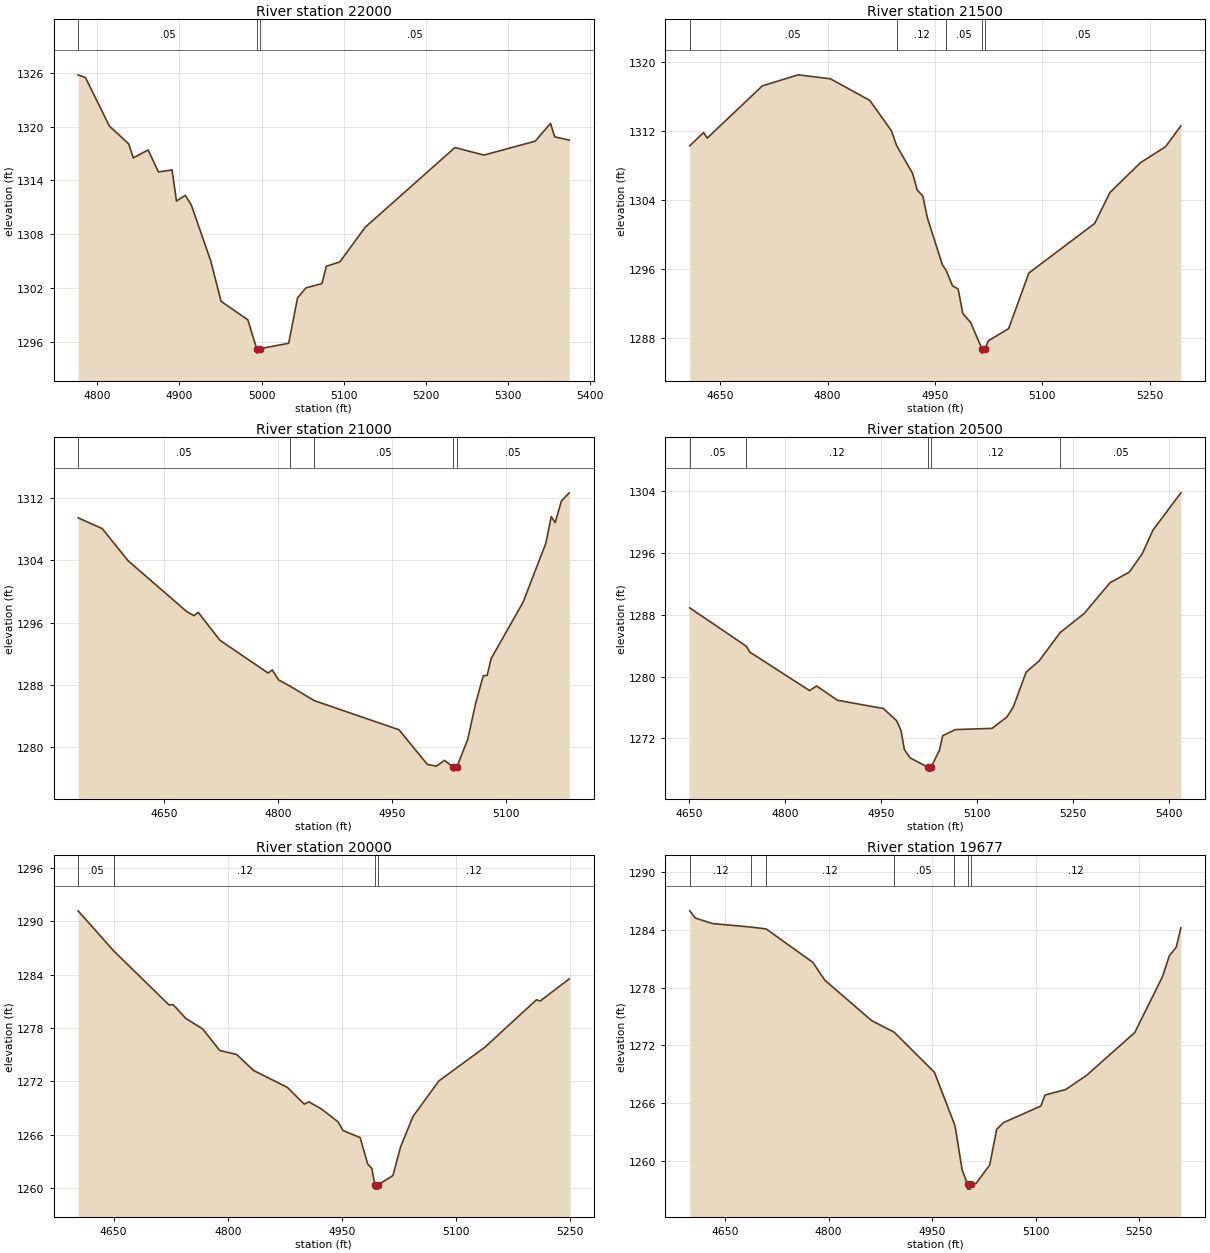
Type RM Length L Ch R = 1,22000,500,500,500
BEGIN DESCRIPTION:
HICKORY MT BRANCH 44.0
END DESCRIPTION:
XS GIS Cut Line= 3
      2803955.73     10204503.09      2804161.14     10204415.26
      2804255.69     10204053.10
#Sta/Elev= 30
  4776.6 1325.76  4785.6 1325.45  4814.7 1320.05  4838.3 1318.06  4843.7 1316.51
  4861.8 1317.39  4874.4 1314.94  4890.9 1315.17  4896.3 1311.70  4907.1 1312.34
  4914.5 1311.23  4938.1 1305.01  4950.6 1300.53  4983.2 1298.47  4993.9 1295.26
  4994.2 1294.76  4998.3 1295.26  5032.9 1295.86  5043.6 1300.90  5053.9 1302.03
  5073.4 1302.51  5078.6 1304.43  5095.2 1304.93  5126.2 1308.80  5235.2 1317.66
  5270.5 1316.82  5332.9 1318.37  5351.5 1320.35  5356.6 1318.85  5374.3 1318.49
#Mann=3,-1,0
  4776.6    0.05       0  4993.9    0.05       0  4998.3    0.05       0
Bank Sta=4993.9,4998.3
Exp/Cntr=0.3,0.1

Type RM Length L Ch R = 1,21500,500,500,500
BEGIN DESCRIPTION:
HICKORY MT BRANCH 43.0
END DESCRIPTION:
XS GIS Cut Line= 4
      2804559.40     10204774.44      2804576.96     10204469.06
      2804520.98     10204402.70      2804305.67     10204203.10
#Sta/Elev= 30
  4607.3 1310.31  4626.7 1311.85  4631.7 1311.20  4708.8 1317.28  4758.9 1318.56
  4803.9 1318.10  4859.0 1315.58  4889.1 1312.06  4896.6 1310.30  4918.7 1307.12
  4925.2 1305.17  4933.0 1304.47  4939.5 1301.90  4960.3 1296.50  4965.6 1295.83
  4974.6 1294.03  4982.4 1293.66  4988.9 1290.82  5000.0 1289.75  5015.6 1286.71
  5015.9 1286.21  5020.0 1286.71  5024.6 1287.64  5052.9 1289.06  5081.3 1295.53
  5173.1 1301.28  5194.6 1304.89  5237.2 1308.35  5272.3 1310.21  5293.6 1312.63
#Mann=5,-1,0
  4607.3    0.05       0  4896.6    0.12       0  4965.6    0.05       0
  5015.6    0.05       0  5020.0    0.05       0
Bank Sta=5015.6,5020
Exp/Cntr=0.3,0.1

Type RM Length L Ch R = 1,21000,500,500,500
BEGIN DESCRIPTION:
HICKORY MT BRANCH 42.0
END DESCRIPTION:
XS GIS Cut Line= 3
      2804705.67     10204553.13      2804897.96     10204131.29
      2804855.69     10203953.13
#Sta/Elev= 30
  4536.4 1309.48  4568.2 1308.09  4602.4 1303.94  4679.3 1297.44  4689.0 1296.89
  4694.5 1297.33  4723.2 1293.73  4786.6 1289.52  4792.1 1289.93  4800.2 1288.65
  4815.0 1287.86  4847.2 1285.98  4958.9 1282.23  4996.3 1277.77  5008.4 1277.55
  5018.7 1278.30  5030.6 1277.41  5030.9 1276.91  5035.0 1277.41  5049.5 1281.00
  5059.8 1285.60  5069.9 1289.17  5075.0 1289.22  5080.3 1291.38  5122.4 1298.64
  5152.3 1306.20  5159.4 1309.64  5164.6 1308.86  5172.8 1311.64  5183.1 1312.69
#Mann=5,-1,0
  4536.4    0.05       0  4815.0    0.12       0  4847.2    0.05       0
  5030.6    0.05       0  5035.0    0.05       0
Bank Sta=5030.6,5035
Exp/Cntr=0.3,0.1

Type RM Length L Ch R = 1,20500,500,500,500
BEGIN DESCRIPTION:
HICKORY MT BRANCH 41.0
END DESCRIPTION:
XS GIS Cut Line= 3
      2805005.69     10204453.11      2805340.65     10204353.03
      2805755.66     10204303.11
#Sta/Elev= 30
  4650.4 1288.90  4738.9 1283.93  4744.3 1283.17  4837.8 1278.18  4848.7 1278.78
  4881.3 1276.93  4953.1 1275.86  4973.9 1274.27  4980.7 1272.99  4985.9 1270.54
  4994.8 1269.47  5023.0 1268.25  5023.3 1267.75  5027.2 1267.75  5027.5 1268.25
  5040.7 1270.46  5045.8 1272.34  5065.5 1273.13  5122.9 1273.29  5146.1 1274.76
  5156.1 1276.05  5176.3 1280.59  5196.4 1282.02  5229.4 1285.71  5266.9 1288.17
  5307.2 1292.15  5337.4 1293.53  5357.6 1295.90  5374.4 1298.97  5418.0 1303.80
#Mann=5,-1,0
  4650.4    0.05       0  4738.9    0.12       0  5023.0    0.07       0
  5027.5    0.12       0  5229.4    0.05       0
Bank Sta=5023,5027.5
Exp/Cntr=0.3,0.1

Type RM Length L Ch R = 1,20000,323,323,323
BEGIN DESCRIPTION:
HICKORY MT BRANCH 40.0
END DESCRIPTION:
XS GIS Cut Line= 3
      2805005.67     10204553.10      2805358.84     10204733.55
      2805605.67     10204703.11
#Sta/Elev= 30
  4603.4 1291.17  4650.6 1286.63  4722.8 1280.60  4728.4 1280.62  4745.0 1279.07
  4767.2 1277.89  4789.5 1275.47  4811.7 1275.03  4833.9 1273.23  4878.3 1271.33
  4900.6 1269.44  4906.6 1269.70  4922.8 1268.92  4945.0 1267.45  4951.5 1266.48
  4974.0 1265.68  4983.8 1262.74  4989.4 1262.19  4993.2 1260.39  4993.5 1259.89
  4997.4 1259.89  4997.7 1260.39  5017.0 1261.41  5027.0 1264.61  5043.3 1268.04
  5077.4 1272.05  5137.9 1275.84  5205.6 1281.17  5210.7 1281.04  5248.7 1283.52
#Mann=4,-1,0
  4603.4    0.05       0  4650.6    0.12       0  4993.2    0.07       0
  4997.7    0.12       0
Bank Sta=4993.2,4997.7
Exp/Cntr=0.3,0.1

Type RM Length L Ch R = 1,19677,541,541,541
BEGIN DESCRIPTION:
Mapping XS 4f6875de
END DESCRIPTION:
XS GIS Cut Line= 3
      2804929.65     10204956.29      2805179.24     10205053.95
      2805622.39     10205043.14
#Sta/Elev= 30
  4598.9 1285.98  4607.3 1285.22  4631.8 1284.66  4688.0 1284.29  4709.6 1284.10
  4777.2 1280.63  4794.7 1278.77  4862.3 1274.59  4895.0 1273.38  4953.4 1269.21
  4981.1 1264.05  4983.4 1263.57  4993.4 1259.09  5001.2 1257.59  5001.5 1257.09
  5005.4 1257.09  5005.7 1257.59  5013.4 1257.67  5033.4 1259.60  5043.4 1263.29
  5053.4 1264.00  5107.4 1265.71  5113.4 1266.86  5143.4 1267.43  5173.5 1268.89
  5243.5 1273.35  5283.5 1279.13  5293.5 1281.31  5303.5 1282.21  5310.2 1284.21
#Mann=7,-1,0
  4598.9    0.12       0  4688.0    0.05       0  4709.6    0.12       0
  4895.0    0.05       0  4981.1    0.12       0  5001.2    0.07       0
  5005.7    0.12       0
Bank Sta=5001.2,5005.7
Exp/Cntr=0.3,0.1

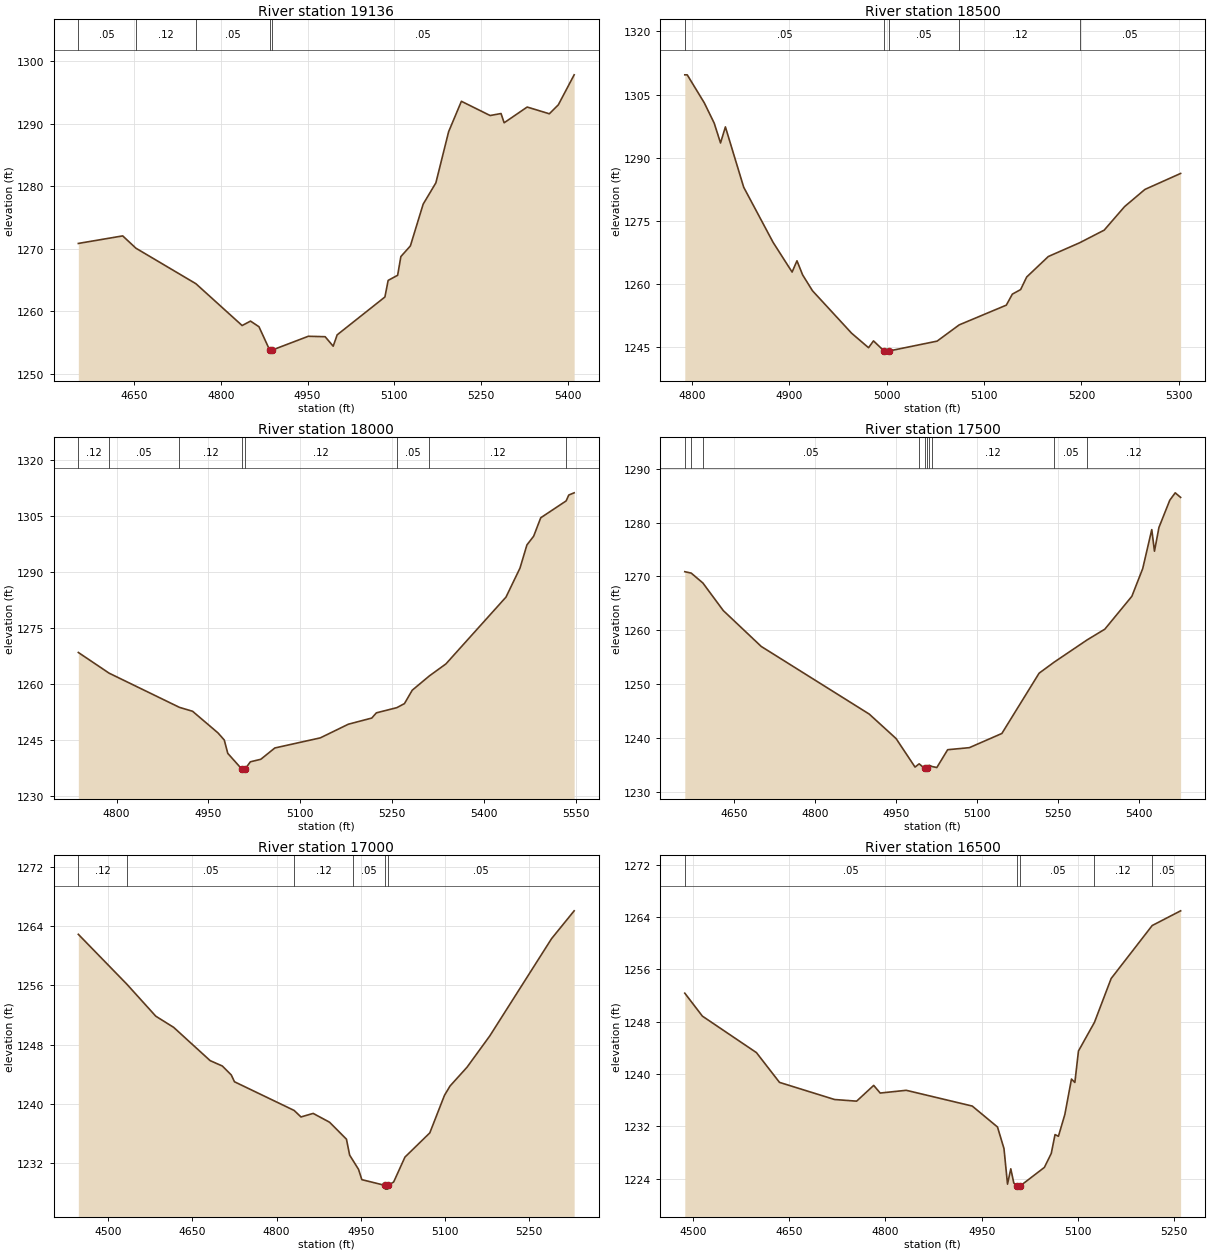
Type RM Length L Ch R = 1,19136,636,636,636
BEGIN DESCRIPTION:
Mapping XS c5273171
END DESCRIPTION:
XS GIS Cut Line= 4
      2804864.56     10205227.55      2805222.64     10205498.83
      2805428.80     10205607.34      2805591.09     10205542.42
#Sta/Elev= 30
  4553.8 1270.84  4630.5 1272.05  4653.3 1270.08  4757.0 1264.39  4836.9 1257.69
  4851.4 1258.40  4866.0 1257.50  4884.5 1253.77  4884.8 1253.27  4889.1 1253.77
  4951.3 1255.97  4980.4 1255.90  4994.3 1254.38  5001.2 1256.20  5083.7 1262.26
  5089.3 1264.92  5105.7 1265.74  5111.3 1268.74  5127.7 1270.44  5149.8 1277.13
  5171.8 1280.55  5193.8 1288.73  5215.9 1293.61  5265.6 1291.33  5284.4 1291.65
  5289.8 1290.17  5329.6 1292.69  5367.9 1291.61  5383.4 1293.04  5410.8 1297.85
#Mann=5,-1,0
  4553.8    0.05       0  4653.3    0.12       0  4757.0    0.05       0
  4884.5    0.05       0  4889.1    0.05       0
Bank Sta=4884.5,4889.1
Exp/Cntr=0.3,0.1

Type RM Length L Ch R = 1,18500,500,500,500
BEGIN DESCRIPTION:
HICKORY MT BRANCH 37.0
END DESCRIPTION:
XS GIS Cut Line= 3
      2804855.72     10205803.12      2805061.34     10205830.28
      2805305.67     10205653.12
#Sta/Elev= 30
  4792.6 1309.69  4795.1 1309.69  4812.7 1303.00  4822.8 1298.21  4829.3 1293.50
  4834.3 1297.32  4853.1 1282.98  4883.3 1269.88  4902.8 1262.83  4907.8 1265.51
  4913.6 1262.16  4923.7 1258.40  4964.0 1248.28  4981.3 1244.86  4986.4 1246.48
  4997.3 1244.07  4997.6 1243.57  5002.1 1244.07  5051.7 1246.42  5074.4 1250.28
  5122.8 1254.97  5129.0 1257.59  5137.5 1258.67  5143.7 1261.65  5165.9 1266.52
  5198.2 1269.80  5223.3 1272.79  5244.2 1278.37  5265.1 1282.46  5301.8 1286.26
#Mann=5,-1,0
  4792.6    0.05       0  4997.3    0.05       0  5002.1    0.05       0
  5074.4    0.12       0  5198.2    0.05       0
Bank Sta=4997.3,5002.1
Exp/Cntr=0.3,0.1

Type RM Length L Ch R = 1,18000,500,500,500
BEGIN DESCRIPTION:
HICKORY MT BRANCH 36.0
END DESCRIPTION:
XS GIS Cut Line= 3
      2805405.69     10206353.07      2805475.43     10206100.01
      2805705.71     10205603.07
#Sta/Elev= 30
  4737.5 1268.43  4787.9 1262.89  4902.7 1253.76  4924.2 1252.71  4965.7 1246.93
  4976.0 1245.02  4981.7 1241.46  5004.9 1237.21  5005.2 1236.71  5009.7 1237.21
  5018.6 1239.20  5035.7 1239.88  5058.6 1242.90  5132.9 1245.60  5178.7 1249.25
  5217.0 1250.90  5224.5 1252.29  5258.0 1253.68  5270.4 1254.76  5283.1 1258.34
  5311.0 1262.15  5338.2 1265.38  5436.3 1283.23  5459.2 1290.99  5470.5 1297.18
  5481.5 1299.51  5493.1 1304.44  5534.6 1308.95  5538.9 1310.52  5547.7 1311.11
#Mann=8,-1,0
  4737.5    0.12       0  4787.9    0.05       0  4902.7    0.12       0
  5004.9    0.07       0  5009.7    0.12       0  5258.0    0.05       0
  5311.0    0.12       0  5534.6    0.05       0
Bank Sta=5004.9,5009.7
Exp/Cntr=0.3,0.1

Type RM Length L Ch R = 1,17500,500,500,500
BEGIN DESCRIPTION:
HICKORY MT BRANCH 35.0
END DESCRIPTION:
XS GIS Cut Line= 3
      2805605.70     10206503.10      2805951.86     10206228.59
      2805905.69     10205753.13
#Sta/Elev= 30
  4558.2 1270.89  4570.1 1270.63  4591.8 1268.79  4629.5 1263.69  4700.0 1257.03
  4900.3 1244.49  4950.0 1239.96  4985.2 1234.67  4992.8 1235.27  5003.1 1234.42
  5003.4 1233.92  5008.0 1234.42  5011.4 1235.01  5016.9 1234.77  5025.6 1234.59
  5045.7 1237.89  5085.9 1238.27  5146.2 1240.90  5215.3 1252.08  5243.6 1254.15
  5304.2 1258.24  5337.1 1260.23  5387.3 1266.33  5407.4 1271.47  5424.2 1278.69
  5429.2 1274.69  5437.5 1279.09  5457.6 1284.14  5467.7 1285.51  5477.7 1284.66
#Mann=10,-1,0
  4558.2    0.05       0  4570.1    0.12       0  4591.8    0.05       0
  4992.8    0.12       0  5003.1    0.07       0  5008.0    0.12       0
  5011.4    0.05       0  5016.9    0.12       0  5243.6    0.05       0
  5304.2    0.12       0
Bank Sta=5003.1,5008
Exp/Cntr=0.3,0.1

Type RM Length L Ch R = 1,17000,500,500,500
BEGIN DESCRIPTION:
HICKORY MT BRANCH 34.0
END DESCRIPTION:
XS GIS Cut Line= 3
      2805955.67     10206603.12      2806437.66     10206331.82
      2806405.68     10206003.07
#Sta/Elev= 30
  4446.9 1262.90  4533.1 1256.19  4584.9 1251.85  4616.8 1250.34  4681.8 1245.85
  4703.4 1245.13  4719.4 1243.92  4725.1 1243.00  4831.4 1239.13  4843.6 1238.25
  4865.3 1238.73  4894.5 1237.54  4924.6 1235.25  4930.3 1233.10  4936.0 1232.41
  4946.2 1231.17  4952.0 1229.79  4993.5 1229.01  4993.9 1228.51  4998.1 1228.51
  4998.4 1229.01  5008.7 1229.47  5028.8 1232.83  5073.1 1236.10  5099.2 1241.16
  5109.2 1242.43  5139.4 1244.96  5180.0 1249.19  5290.1 1262.32  5330.3 1266.07
#Mann=6,-1,0
  4446.9    0.12       0  4533.1    0.05       0  4831.4    0.12       0
  4936.0    0.05       0  4993.5    0.05       0  4998.4    0.05       0
Bank Sta=4993.5,4998.4
Exp/Cntr=0.3,0.1

Type RM Length L Ch R = 1,16500,500,500,500
BEGIN DESCRIPTION:
HICKORY MT BRANCH 33.0
END DESCRIPTION:
XS GIS Cut Line= 3
      2806205.73     10206703.10      2806710.76     10206616.53
      2806955.70     10206703.12
#Sta/Elev= 30
  4487.6 1252.35  4515.0 1248.84  4599.2 1243.26  4635.1 1238.71  4720.9 1236.09
  4755.2 1235.84  4781.8 1238.25  4791.9 1237.08  4832.5 1237.50  4935.3 1235.09
  4974.6 1231.89  4984.7 1228.59  4990.2 1223.15  4995.3 1225.50  5000.0 1223.32
  5005.2 1222.89  5005.5 1222.39  5010.1 1222.89  5047.6 1225.71  5058.3 1227.84
  5064.2 1230.73  5069.5 1230.47  5079.5 1233.81  5089.8 1239.22  5095.1 1238.70
  5100.7 1243.51  5125.6 1247.89  5151.6 1254.59  5215.5 1262.69  5259.8 1264.94
#Mann=5,-1,0
  4487.6    0.05       0  5005.2    0.05       0  5010.1    0.05       0
  5125.6    0.12       0  5215.5    0.05       0
Bank Sta=5005.2,5010.1
Exp/Cntr=0.3,0.1

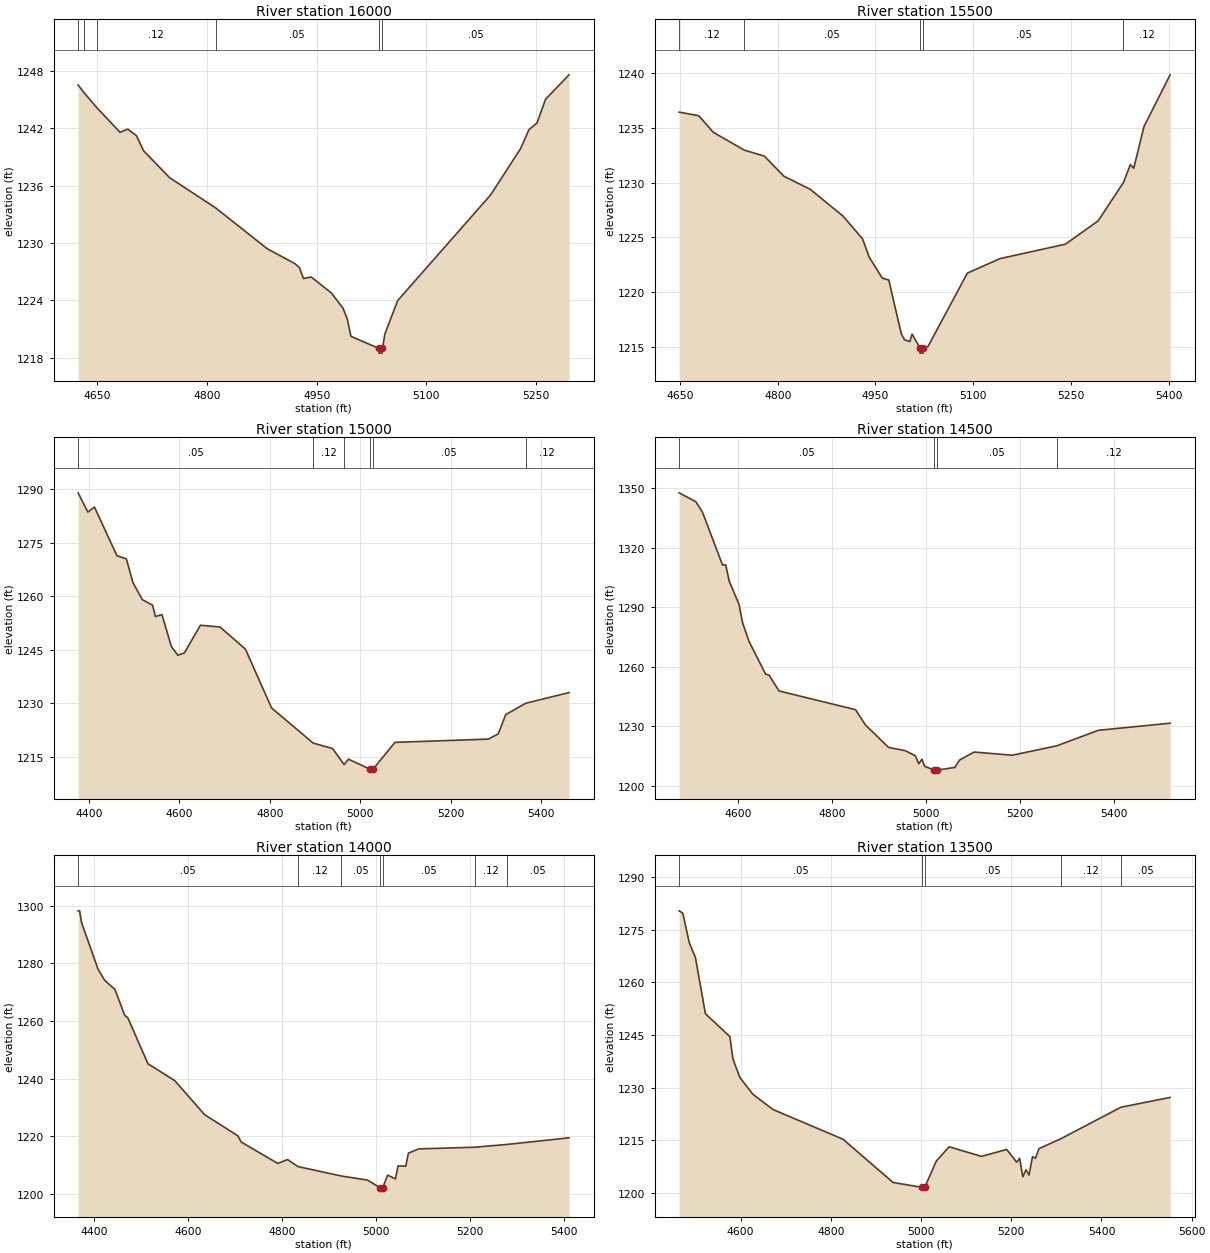
Type RM Length L Ch R = 1,16000,500,500,500
BEGIN DESCRIPTION:
HICKORY MT BRANCH 32.0
END DESCRIPTION:
XS GIS Cut Line= 3
      2806205.70     10206903.12      2806536.13     10207082.95
      2806805.67     10207203.10
#Sta/Elev= 30
  4623.8 1246.54  4632.4 1245.69  4649.0 1244.20  4681.2 1241.58  4691.7 1241.92
  4703.5 1241.24  4713.5 1239.64  4749.0 1236.83  4811.9 1233.67  4882.6 1229.39
  4919.8 1227.86  4926.3 1227.44  4932.0 1226.28  4942.5 1226.44  4970.0 1224.78
  4986.1 1223.17  4991.8 1222.07  4996.9 1220.23  5035.0 1218.97  5035.4 1218.47
  5039.6 1218.47  5040.0 1218.97  5043.3 1220.47  5060.8 1223.97  5187.9 1235.03
  5228.8 1239.87  5240.4 1241.87  5251.3 1242.56  5263.0 1245.04  5295.1 1247.60
#Mann=6,-1,0
  4623.8    0.12       0  4632.4    0.05       0  4649.0    0.12       0
  4811.9    0.05       0  5035.0    0.05       0  5040.0    0.05       0
Bank Sta=5035,5040
Exp/Cntr=0.3,0.1

Type RM Length L Ch R = 1,15500,500,500,500
BEGIN DESCRIPTION:
HICKORY MT BRANCH 31.0
END DESCRIPTION:
XS GIS Cut Line= 3
      2805905.69     10207453.11      2806255.08     10207488.74
      2806655.70     10207453.11
#Sta/Elev= 30
  4648.8 1236.45  4678.9 1236.12  4701.1 1234.61  4748.6 1232.98  4779.5 1232.43
  4809.6 1230.59  4849.8 1229.40  4900.2 1226.95  4930.2 1224.87  4940.3 1223.21
  4960.4 1221.28  4970.5 1221.10  4989.7 1216.18  4994.7 1215.63  5002.8 1215.48
  5006.3 1216.16  5018.0 1214.92  5018.4 1214.42  5023.0 1214.42  5023.4 1214.92
  5030.7 1215.03  5091.0 1221.73  5141.2 1223.06  5241.6 1224.38  5291.8 1226.51
  5330.6 1230.02  5341.3 1231.66  5346.4 1231.32  5362.0 1235.11  5402.2 1239.86
#Mann=5,-1,0
  4648.8    0.12       0  4748.6    0.05       0  5018.0    0.05       0
  5023.4    0.05       0  5330.6    0.12       0
Bank Sta=5018,5023.4
Exp/Cntr=0.3,0.1

Type RM Length L Ch R = 1,15000,500,500,500
BEGIN DESCRIPTION:
HICKORY MT BRANCH 30.0
END DESCRIPTION:
XS GIS Cut Line= 3
      2805655.68     10208353.11      2806148.06     10207969.46
      2806555.70     10207753.10
#Sta/Elev= 30
  4375.8 1288.93  4397.5 1283.54  4412.0 1284.95  4461.7 1271.31  4482.6 1270.42
  4497.0 1263.80  4517.8 1259.01  4540.5 1257.45  4546.8 1254.29  4561.3 1254.81
  4582.1 1245.87  4596.5 1243.42  4611.0 1244.09  4646.3 1251.83  4689.7 1251.33
  4745.8 1245.15  4803.7 1228.65  4895.7 1218.81  4938.5 1217.29  4964.1 1212.81
  4973.8 1214.30  5022.1 1211.45  5022.6 1210.95  5027.8 1211.45  5076.6 1219.01
  5283.1 1219.92  5305.1 1221.38  5321.4 1226.76  5365.6 1229.96  5461.5 1232.96
#Mann=6,-1,0
  4375.8    0.05       0  4895.7    0.12       0  4964.1    0.05       0
  5022.1    0.03       0  5027.8    0.05       0  5365.6    0.12       0
Bank Sta=5022.1,5027.8
Exp/Cntr=0.3,0.1

Type RM Length L Ch R = 1,14500,500,500,500
BEGIN DESCRIPTION:
HICKORY MT BRANCH 29.0
END DESCRIPTION:
XS GIS Cut Line= 3
      2806055.66     10208703.14      2806408.33     10208313.16
      2806505.69     10207803.07
#Sta/Elev= 30
  4474.2 1347.62  4509.7 1343.14  4523.9 1337.83  4566.5 1311.25  4573.3 1311.30
  4580.7 1303.12  4601.6 1291.40  4609.1 1282.23  4622.6 1272.87  4658.4 1256.15
  4665.2 1255.80  4686.8 1247.75  4849.7 1238.31  4870.7 1230.63  4920.0 1219.29
  4955.8 1217.64  4976.8 1215.10  4984.2 1211.08  4991.0 1213.34  4996.7 1209.77
  5017.6 1207.84  5018.1 1207.34  5023.3 1207.84  5061.0 1209.21  5071.3 1212.95
  5101.9 1216.96  5183.3 1215.36  5278.3 1220.11  5366.5 1227.92  5519.3 1231.50
#Mann=4,-1,0
  4474.2    0.05       0  5017.6    0.05       0  5023.3    0.05       0
  5278.3    0.12       0
Bank Sta=5017.6,5023.3
Exp/Cntr=0.3,0.1

Type RM Length L Ch R = 1,14000,500,500,500
BEGIN DESCRIPTION:
HICKORY MT BRANCH 28.0
END DESCRIPTION:
XS GIS Cut Line= 3
      2806305.67     10208903.12      2806790.62     10208493.35
      2806980.67     10208128.14
#Sta/Elev= 30
  4365.1 1298.20  4368.4 1298.20  4372.3 1294.23  4407.4 1278.06  4421.7 1274.12
  4443.7 1270.94  4464.6 1261.93  4471.1 1261.12  4514.0 1245.19  4571.2 1239.34
  4634.9 1227.52  4705.5 1220.22  4712.9 1218.04  4790.9 1210.61  4811.7 1211.97
  4833.5 1209.54  4925.6 1206.28  4982.1 1204.84  5008.7 1202.21  5009.1 1201.71
  5014.4 1202.21  5025.1 1206.57  5041.6 1205.26  5047.2 1209.76  5063.7 1209.68
  5069.3 1214.19  5091.4 1215.66  5210.9 1216.24  5279.7 1217.21  5411.7 1219.50
#Mann=7,-1,0
  4365.1    0.05       0  4833.5    0.12       0  4925.6    0.05       0
  5008.7    0.05       0  5014.4    0.05       0  5210.9    0.12       0
  5279.7    0.05       0
Bank Sta=5008.7,5014.4
Exp/Cntr=0.3,0.1

Type RM Length L Ch R = 1,13500,500,500,500
BEGIN DESCRIPTION:
HICKORY MT BRANCH 27.0
END DESCRIPTION:
XS GIS Cut Line= 3
      2806455.72     10208953.09      2806932.87     10208708.25
      2807355.71     10208353.09
#Sta/Elev= 30
  4463.7 1280.35  4471.9 1279.66  4486.1 1271.27  4499.8 1267.04  4521.9 1251.05
  4576.1 1244.55  4582.9 1238.15  4598.5 1232.87  4627.3 1228.11  4671.7 1223.79
  4827.0 1215.33  4938.0 1203.02  5002.4 1201.63  5002.8 1201.13  5008.1 1201.63
  5033.8 1209.11  5062.4 1213.19  5133.9 1210.45  5189.9 1212.43  5212.0 1208.79
  5218.5 1209.91  5225.7 1204.65  5232.8 1206.63  5239.4 1205.13  5247.1 1210.35
  5253.7 1209.92  5261.4 1212.65  5310.2 1215.48  5442.9 1224.43  5552.2 1227.24
#Mann=5,-1,0
  4463.7    0.05       0  5002.4    0.05       0  5008.1    0.05       0
  5310.2    0.12       0  5442.9    0.05       0
Bank Sta=5002.4,5008.1
Exp/Cntr=0.3,0.1

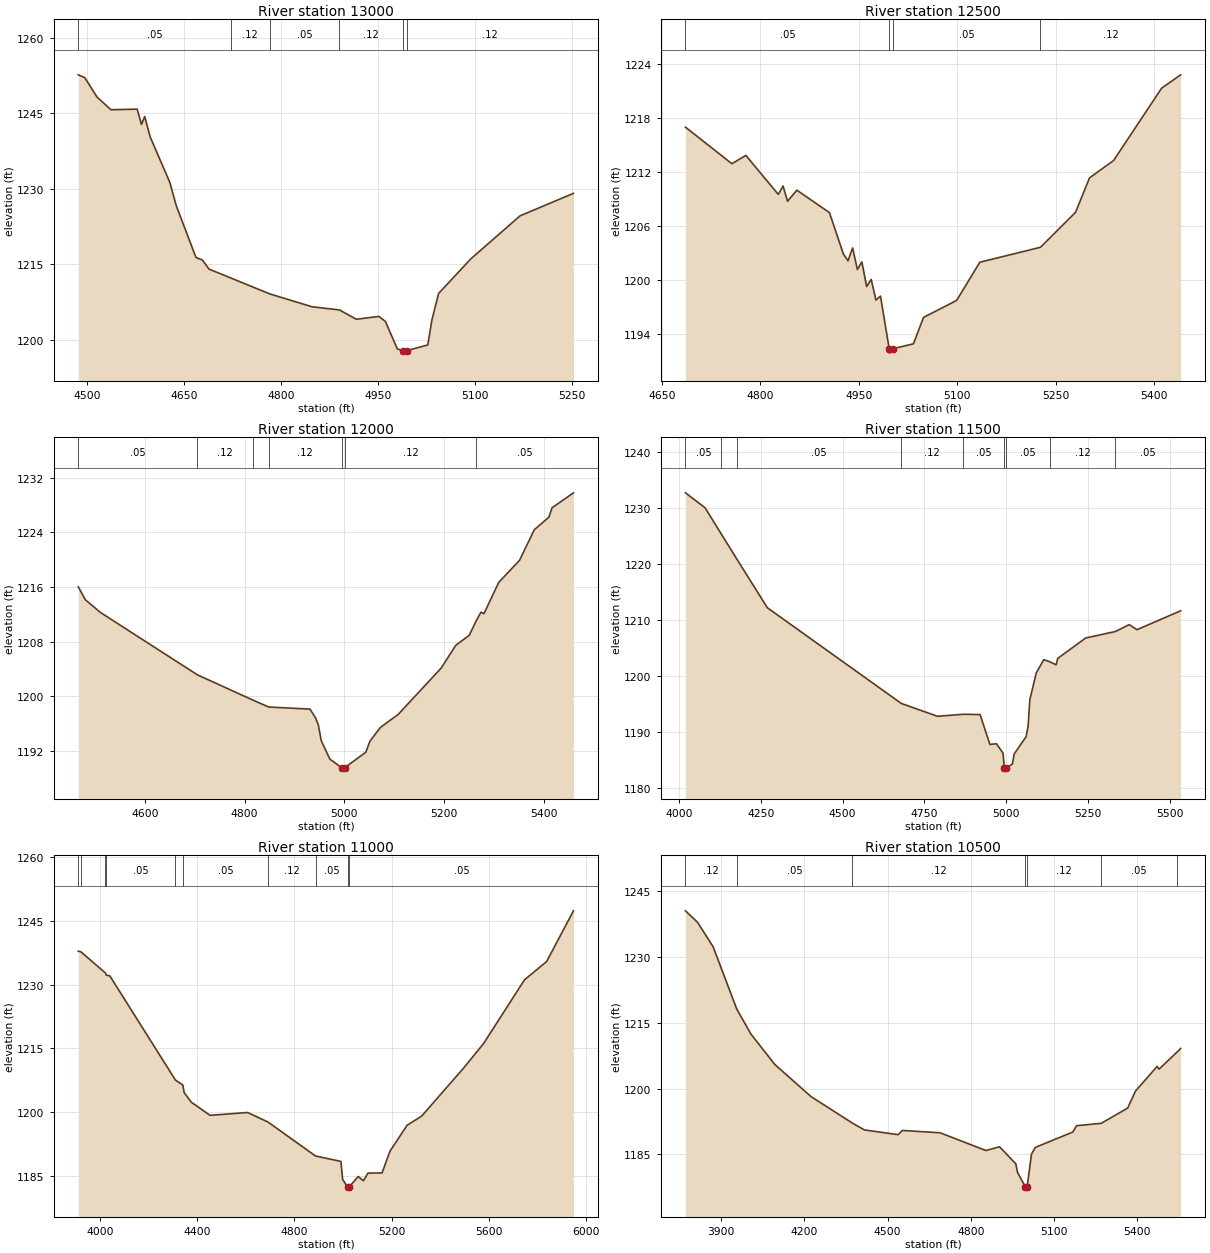
Type RM Length L Ch R = 1,13000,500,500,500
BEGIN DESCRIPTION:
HICKORY MT BRANCH 26.0
END DESCRIPTION:
XS GIS Cut Line= 3
      2806605.68     10209203.11      2807113.79     10209125.58
      2807355.67     10209053.11
#Sta/Elev= 30
  4486.0 1252.61  4496.1 1252.04  4515.2 1248.16  4536.6 1245.68  4577.1 1245.80
  4583.8 1242.75  4588.8 1244.34  4597.3 1240.27  4627.6 1231.28  4637.7 1226.60
  4668.1 1216.35  4678.2 1215.83  4688.3 1214.04  4722.3 1212.26  4782.2 1209.12
  4847.9 1206.55  4890.2 1205.93  4916.4 1204.08  4951.3 1204.64  4961.4 1203.64
  4979.9 1198.16  4988.8 1197.85  4989.3 1197.35  4994.7 1197.85  5027.0 1198.98
  5033.3 1203.91  5043.7 1209.19  5093.2 1216.02  5169.8 1224.61  5252.5 1229.08
#Mann=6,-1,0
  4486.0    0.05       0  4722.3    0.12       0  4782.2    0.05       0
  4890.2    0.12       0  4988.8    0.07       0  4994.7    0.12       0
Bank Sta=4988.8,4994.7
Exp/Cntr=0.3,0.1

Type RM Length L Ch R = 1,12500,500,500,500
BEGIN DESCRIPTION:
HICKORY MT BRANCH 25.0
END DESCRIPTION:
XS GIS Cut Line= 3
      2806955.66     10209753.14      2807173.68     10209527.30
      2807405.69     10209153.10
#Sta/Elev= 30
  4686.1 1216.96  4756.8 1212.91  4778.1 1213.83  4827.5 1209.51  4834.7 1210.44
  4841.6 1208.75  4855.8 1209.98  4905.4 1207.49  4926.5 1202.92  4933.7 1202.15
  4940.7 1203.58  4947.9 1201.19  4954.8 1202.03  4962.0 1199.30  4969.0 1200.09
  4976.2 1197.80  4983.1 1198.24  4996.4 1192.42  4996.9 1191.92  5002.4 1192.42
  5033.3 1192.95  5048.7 1195.88  5099.1 1197.76  5134.4 1201.99  5226.8 1203.65
  5280.2 1207.52  5301.5 1211.34  5338.1 1213.26  5411.3 1221.28  5440.3 1222.76
#Mann=4,-1,0
  4686.1    0.05       0  4996.4    0.03       0  5002.4    0.05       0
  5226.8    0.12       0
Bank Sta=4996.4,5002.4
Exp/Cntr=0.3,0.1

Type RM Length L Ch R = 1,12000,500,500,500
BEGIN DESCRIPTION:
HICKORY MT BRANCH 24.0
END DESCRIPTION:
XS GIS Cut Line= 3
      2807155.64     10209903.13      2807638.19     10209676.06
      2807905.71     10209303.08
#Sta/Elev= 30
  4466.7 1216.01  4480.9 1214.12  4511.0 1212.27  4705.5 1203.13  4816.9 1199.43
  4848.4 1198.42  4930.9 1198.12  4942.0 1196.86  4947.9 1195.76  4953.4 1193.53
  4970.7 1190.81  4994.5 1189.54  4995.0 1189.04  5000.6 1189.54  5042.7 1191.80
  5051.2 1193.43  5072.1 1195.44  5107.7 1197.34  5193.7 1204.11  5223.2 1207.46
  5250.2 1208.94  5264.3 1211.07  5273.5 1212.29  5279.7 1212.10  5309.1 1216.66
  5350.9 1219.90  5380.4 1224.37  5409.7 1226.21  5416.0 1227.59  5459.0 1229.78
#Mann=7,-1,0
  4466.7    0.05       0  4705.5    0.12       0  4816.9    0.05       0
  4848.4    0.12       0  4994.5    0.07       0  5000.6    0.12       0
  5264.3    0.05       0
Bank Sta=4994.5,5000.6
Exp/Cntr=0.3,0.1

Type RM Length L Ch R = 1,11500,500,500,500
BEGIN DESCRIPTION:
HICKORY MT BRANCH 23.0
END DESCRIPTION:
XS GIS Cut Line= 3
      2807005.72     10210003.11      2807985.34     10209972.59
      2808105.68     10209453.14
#Sta/Elev= 30
  4019.9 1232.77  4079.9 1230.10  4129.6 1225.39  4177.4 1220.90  4270.0 1212.26
  4679.7 1195.16  4790.2 1192.87  4868.8 1193.23  4920.3 1193.18  4950.3 1187.85
  4970.3 1187.97  4990.3 1186.30  4994.6 1183.58  4995.1 1183.08  5000.7 1183.58
  5019.3 1184.39  5024.4 1186.13  5061.0 1189.25  5067.1 1191.11  5072.2 1195.81
  5091.8 1200.59  5114.9 1202.99  5134.2 1202.58  5152.5 1202.06  5157.6 1203.21
  5243.0 1206.85  5333.9 1208.01  5376.1 1209.24  5399.8 1208.33  5533.2 1211.71
#Mann=9,-1,0
  4019.9    0.05       0  4129.6    0.12       0  4177.4    0.05       0
  4679.7    0.12       0  4868.8    0.05       0  4994.6    0.05       0
  5000.7    0.05       0  5134.2    0.12       0  5333.9    0.05       0
Bank Sta=4994.6,5000.7
Exp/Cntr=0.3,0.1

Type RM Length L Ch R = 1,11000,500,500,500
BEGIN DESCRIPTION:
HICKORY MT BRANCH 22.0
END DESCRIPTION:
XS GIS Cut Line= 3
      2806955.64     10210053.09      2807963.66     10210467.82
      2808905.70     10210353.11
#Sta/Elev= 30
  3910.0 1237.84  3920.8 1237.69  4021.5 1232.72  4025.7 1232.19  4039.8 1232.04
  4310.0 1207.55  4340.5 1206.39  4345.8 1204.61  4375.2 1202.35  4452.5 1199.26
  4607.0 1199.93  4690.8 1197.70  4886.8 1189.71  4991.4 1188.43  4998.4 1184.20
  5019.0 1182.42  5019.5 1181.92  5025.3 1182.42  5062.5 1184.89  5084.0 1183.89
  5102.8 1185.69  5160.6 1185.72  5193.4 1190.83  5264.0 1196.94  5323.9 1199.08
  5497.3 1210.42  5579.0 1216.15  5747.5 1231.12  5838.2 1235.39  5949.0 1247.32
#Mann=10,-1,0
  3910.0    0.12       0  3920.8    0.05       0  4021.5    0.12       0
  4025.7    0.05       0  4310.0    0.12       0  4340.5    0.05       0
  4690.8    0.12       0  4886.8    0.05       0  5019.0    0.03       0
  5025.3    0.05       0
Bank Sta=5019,5025.3
Exp/Cntr=0.3,0.1

Type RM Length L Ch R = 1,10500,500,500,500
BEGIN DESCRIPTION:
HICKORY MT BRANCH 21.0
END DESCRIPTION:
XS GIS Cut Line= 3
      2806905.69     10210153.12      2807904.12     10210868.39
      2808305.67     10211253.10
#Sta/Elev= 30
  3771.8 1240.56  3814.8 1237.98  3871.3 1232.38  3956.2 1218.20  4007.6 1212.44
  4093.6 1205.51  4223.8 1198.19  4372.6 1192.15  4416.7 1190.56  4538.3 1189.48
  4553.0 1190.44  4689.3 1189.91  4854.3 1185.86  4903.5 1186.71  4962.0 1182.84
  4968.2 1180.90  4996.6 1177.55  4997.1 1177.05  5003.0 1177.55  5018.5 1185.01
  5032.6 1186.58  5167.2 1190.07  5181.4 1191.53  5269.6 1192.06  5365.1 1195.54
  5393.4 1199.43  5471.4 1205.06  5478.3 1204.42  5543.7 1208.37  5556.1 1209.16
#Mann=7,-1,0
  3771.8    0.12       0  3956.2    0.05       0  4372.6    0.12       0
  4996.6    0.07       0  5003.0    0.12       0  5269.6    0.05       0
  5543.7    0.12       0
Bank Sta=4996.6,5003
Exp/Cntr=0.3,0.1