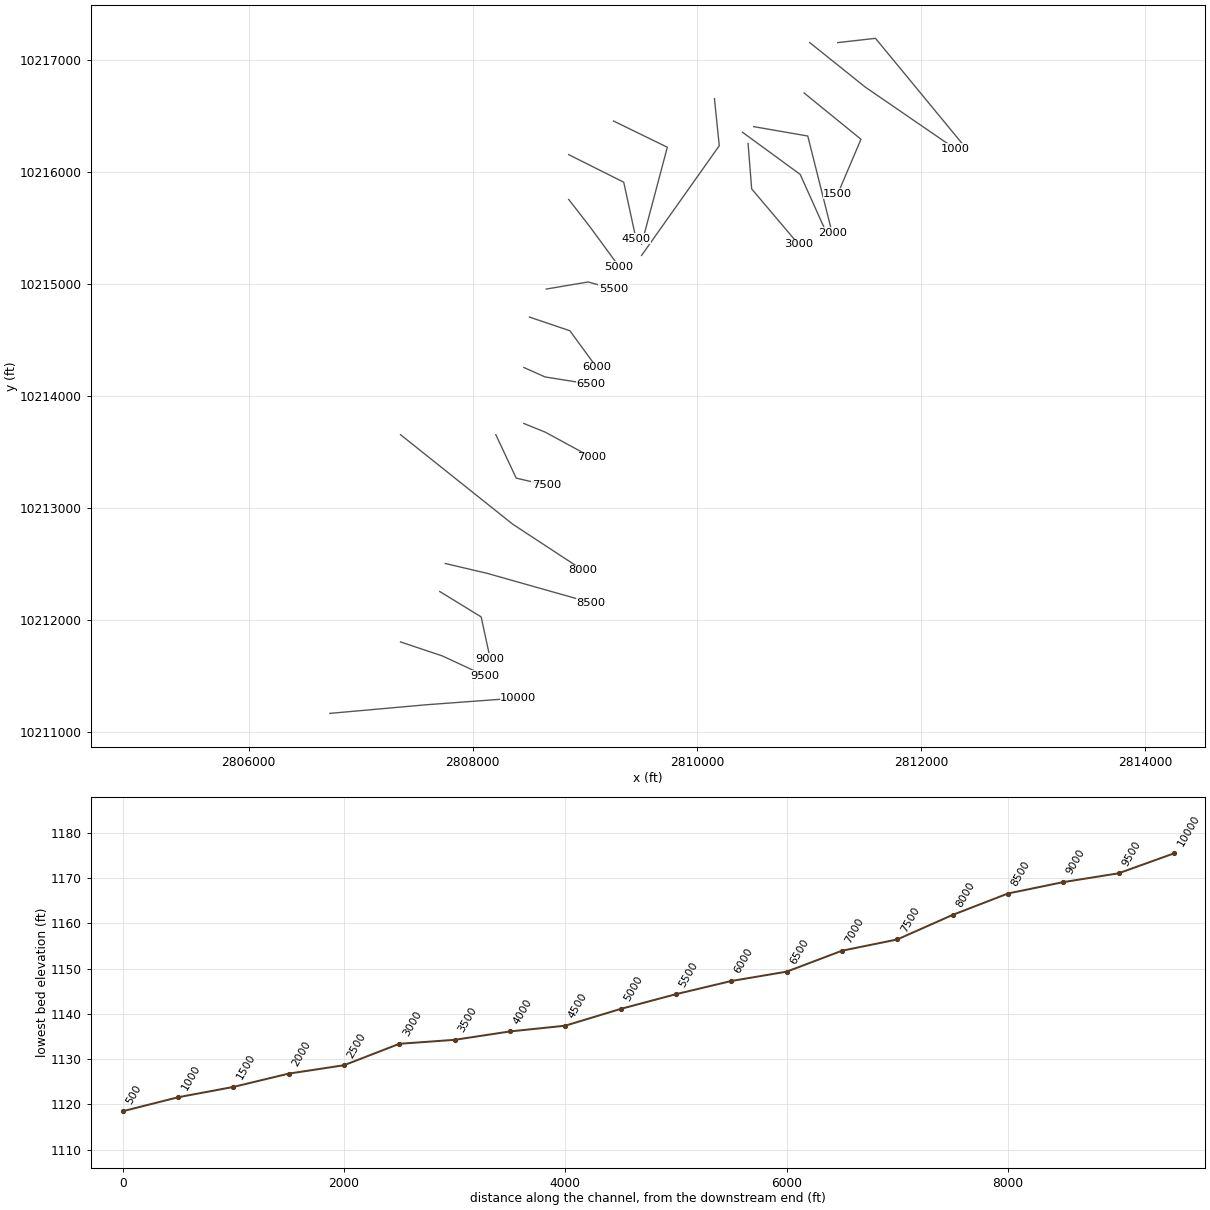
HEC-RAS study HICKORY MT BRANCH.prj: HICKORY MT BRANCH Base Level Engineering

--- HICKORY MT BRANCH.g01 (geometry) --- (continued)

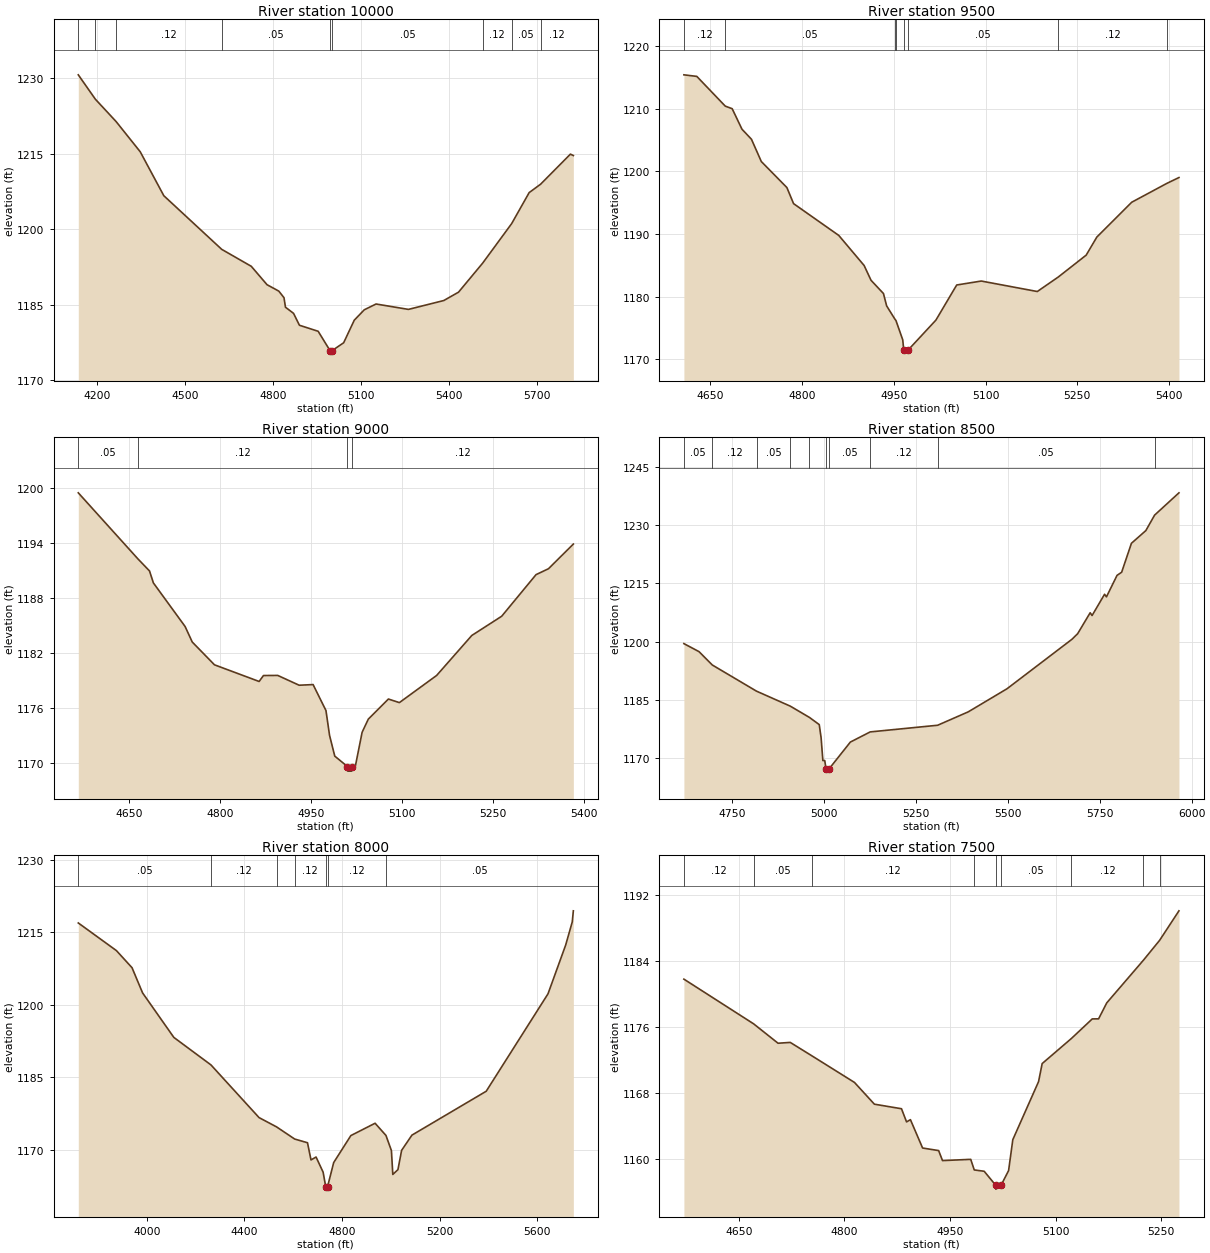
Type RM Length L Ch R = 1,10000,500,500,500
BEGIN DESCRIPTION:
HICKORY MT BRANCH 20.0
END DESCRIPTION:
XS GIS Cut Line= 3
      2806725.64     10211165.49      2807585.31     10211242.37
      2808405.67     10211303.11
#Sta/Elev= 30
  4136.9 1230.70  4195.0 1225.86  4265.6 1221.42  4347.8 1215.41  4428.1 1206.68
  4625.3 1196.02  4726.0 1192.65  4779.5 1189.00  4819.7 1187.72  4837.3 1186.42
  4842.4 1184.52  4869.9 1183.30  4889.9 1180.94  4953.7 1179.74  4994.1 1175.90
  4994.6 1175.40  5001.3 1175.90  5040.5 1177.46  5076.7 1181.95  5110.7 1184.01
  5150.8 1185.16  5261.1 1184.09  5381.4 1185.85  5431.6 1187.51  5513.8 1193.28
  5612.5 1201.13  5672.2 1207.30  5711.2 1208.97  5812.6 1214.94  5822.6 1214.66
#Mann=9,-1,0
  4136.9    0.12       0  4195.0    0.05       0  4265.6    0.12       0
  4625.3    0.05       0  4994.1    0.05       0  5001.3    0.05       0
  5513.8    0.12       0  5612.5    0.05       0  5711.2    0.12       0
Bank Sta=4994.1,5001.3
Exp/Cntr=0.3,0.1

Type RM Length L Ch R = 1,9500,500,500,500
BEGIN DESCRIPTION:
HICKORY MT BRANCH 19.0
END DESCRIPTION:
XS GIS Cut Line= 3
      2807355.72     10211803.10      2807728.27     10211678.29
      2808105.70     10211503.11
#Sta/Elev= 30
  4607.1 1215.37  4628.2 1215.12  4674.7 1210.38  4686.0 1209.97  4702.0 1206.70
  4717.5 1205.10  4733.6 1201.55  4775.4 1197.40  4786.3 1194.84  4860.2 1189.77
  4901.6 1184.98  4912.9 1182.62  4933.2 1180.51  4938.4 1178.54  4951.9 1176.43
  4953.7 1176.19  4964.7 1173.13  4966.4 1171.51  4966.9 1171.01  4973.6 1171.51
  5018.9 1176.27  5052.9 1181.87  5093.1 1182.50  5184.6 1180.83  5219.0 1183.15
  5264.5 1186.63  5281.9 1189.51  5338.9 1195.06  5396.2 1198.06  5416.1 1199.00
#Mann=8,-1,0
  4607.1    0.12       0  4674.7    0.05       0  4951.9    0.12       0
  4953.7    0.05       0  4966.4    0.05       0  4973.6    0.05       0
  5219.0    0.12       0  5396.2    0.05       0
Bank Sta=4966.4,4973.6
Exp/Cntr=0.3,0.1

Type RM Length L Ch R = 1,9000,500,500,500
BEGIN DESCRIPTION:
HICKORY MT BRANCH 18.0
END DESCRIPTION:
XS GIS Cut Line= 3
      2807705.68     10212253.11      2808074.84     10212026.63
      2808155.69     10211653.08
#Sta/Elev= 30
  4566.9 1199.48  4665.1 1192.26  4684.2 1190.94  4690.6 1189.63  4742.8 1184.87
  4754.6 1183.17  4791.2 1180.68  4864.7 1178.86  4871.9 1179.51  4895.4 1179.52
  4930.6 1178.45  4953.6 1178.52  4974.8 1175.68  4980.7 1172.97  4989.3 1170.70
  5010.2 1169.56  5010.7 1169.06  5017.0 1169.06  5017.5 1169.56  5023.3 1169.64
  5034.3 1173.30  5044.5 1174.74  5077.6 1176.94  5095.7 1176.55  5157.1 1179.52
  5215.0 1183.89  5264.2 1185.99  5320.8 1190.54  5341.2 1191.18  5382.2 1193.88
#Mann=4,-1,0
  4566.9    0.05       0  4665.1    0.12       0  5010.2    0.07       0
  5017.5    0.12       0
Bank Sta=5010.2,5017.5
Exp/Cntr=0.3,0.1

Type RM Length L Ch R = 1,8500,500,500,500
BEGIN DESCRIPTION:
HICKORY MT BRANCH 17.0
END DESCRIPTION:
XS GIS Cut Line= 3
      2807755.68     10212503.11      2808126.57     10212415.94
      2809055.71     10212153.10
#Sta/Elev= 30
  4619.0 1199.46  4660.1 1197.39  4696.3 1193.94  4816.5 1187.19  4908.4 1183.32
  4960.5 1180.41  4987.1 1178.56  4992.2 1175.16  4997.0 1169.28  5002.1 1169.28
  5005.7 1167.05  5006.2 1166.55  5013.2 1167.05  5071.8 1174.05  5125.7 1176.67
  5309.2 1178.39  5392.5 1181.85  5497.9 1187.81  5674.6 1200.58  5690.1 1202.03
  5724.1 1207.43  5729.3 1206.71  5763.2 1212.20  5768.4 1211.53  5797.2 1217.08
  5809.7 1217.88  5836.3 1225.35  5875.5 1228.63  5899.3 1232.62  5965.6 1238.38
#Mann=10,-1,0
  4619.0    0.05       0  4696.3    0.12       0  4816.5    0.05       0
  4908.4    0.12       0  4960.5    0.05       0  5005.7    0.05       0
  5013.2    0.05       0  5125.7    0.12       0  5309.2    0.05       0
  5899.3    0.12       0
Bank Sta=5005.7,5013.2
Exp/Cntr=0.3,0.1

Type RM Length L Ch R = 1,8000,500,500,500
BEGIN DESCRIPTION:
HICKORY MT BRANCH 16.0
END DESCRIPTION:
XS GIS Cut Line= 3
      2807355.65     10213653.14      2808356.29     10212854.30
      2808981.66     10212443.91
#Sta/Elev= 30
  3719.6 1216.89  3875.8 1211.17  3939.8 1207.63  3983.0 1202.42  4111.1 1193.21
  4263.2 1187.52  4460.2 1176.62  4531.9 1174.70  4606.3 1172.18  4658.7 1171.42
  4673.1 1167.86  4693.9 1168.46  4722.8 1165.32  4733.4 1162.32  4733.9 1161.82
  4740.9 1162.32  4766.0 1167.31  4836.4 1172.90  4935.7 1175.45  4980.2 1172.93
  5002.6 1169.79  5008.3 1164.86  5029.3 1165.85  5044.4 1169.85  5086.6 1172.99
  5391.0 1182.07  5644.2 1202.23  5716.5 1212.31  5743.6 1217.11  5748.0 1219.40
#Mann=7,-1,0
  3719.6    0.05       0  4263.2    0.12       0  4531.9    0.05       0
  4606.3    0.12       0  4733.4    0.05       0  4740.9    0.12       0
  4980.2    0.05       0
Bank Sta=4733.4,4740.9
Exp/Cntr=0.3,0.1

Type RM Length L Ch R = 1,7500,500,500,500
BEGIN DESCRIPTION:
HICKORY MT BRANCH 15.0
END DESCRIPTION:
XS GIS Cut Line= 3
      2808205.69     10213653.10      2808387.49     10213265.40
      2808655.65     10213203.12
#Sta/Elev= 30
  4571.8 1181.80  4670.8 1176.40  4705.6 1174.05  4722.9 1174.15  4754.4 1172.49
  4814.2 1169.31  4842.5 1166.68  4881.0 1166.13  4888.2 1164.54  4893.7 1164.81
  4911.0 1161.38  4933.8 1161.07  4939.3 1159.86  4979.4 1160.01  4984.4 1158.73
  4998.5 1158.57  5014.6 1156.91  5015.1 1156.41  5022.7 1156.91  5033.2 1158.65
  5039.2 1162.39  5075.8 1169.41  5080.9 1171.59  5122.4 1174.62  5152.1 1176.99
  5161.1 1177.00  5172.7 1178.93  5224.8 1184.09  5247.8 1186.49  5275.3 1190.06
#Mann=9,-1,0
  4571.8    0.12       0  4670.8    0.05       0  4754.4    0.12       0
  4984.4    0.05       0  5014.6    0.05       0  5022.7    0.05       0
  5122.4    0.12       0  5224.8    0.05       0  5247.8    0.12       0
Bank Sta=5014.6,5022.7
Exp/Cntr=0.3,0.1

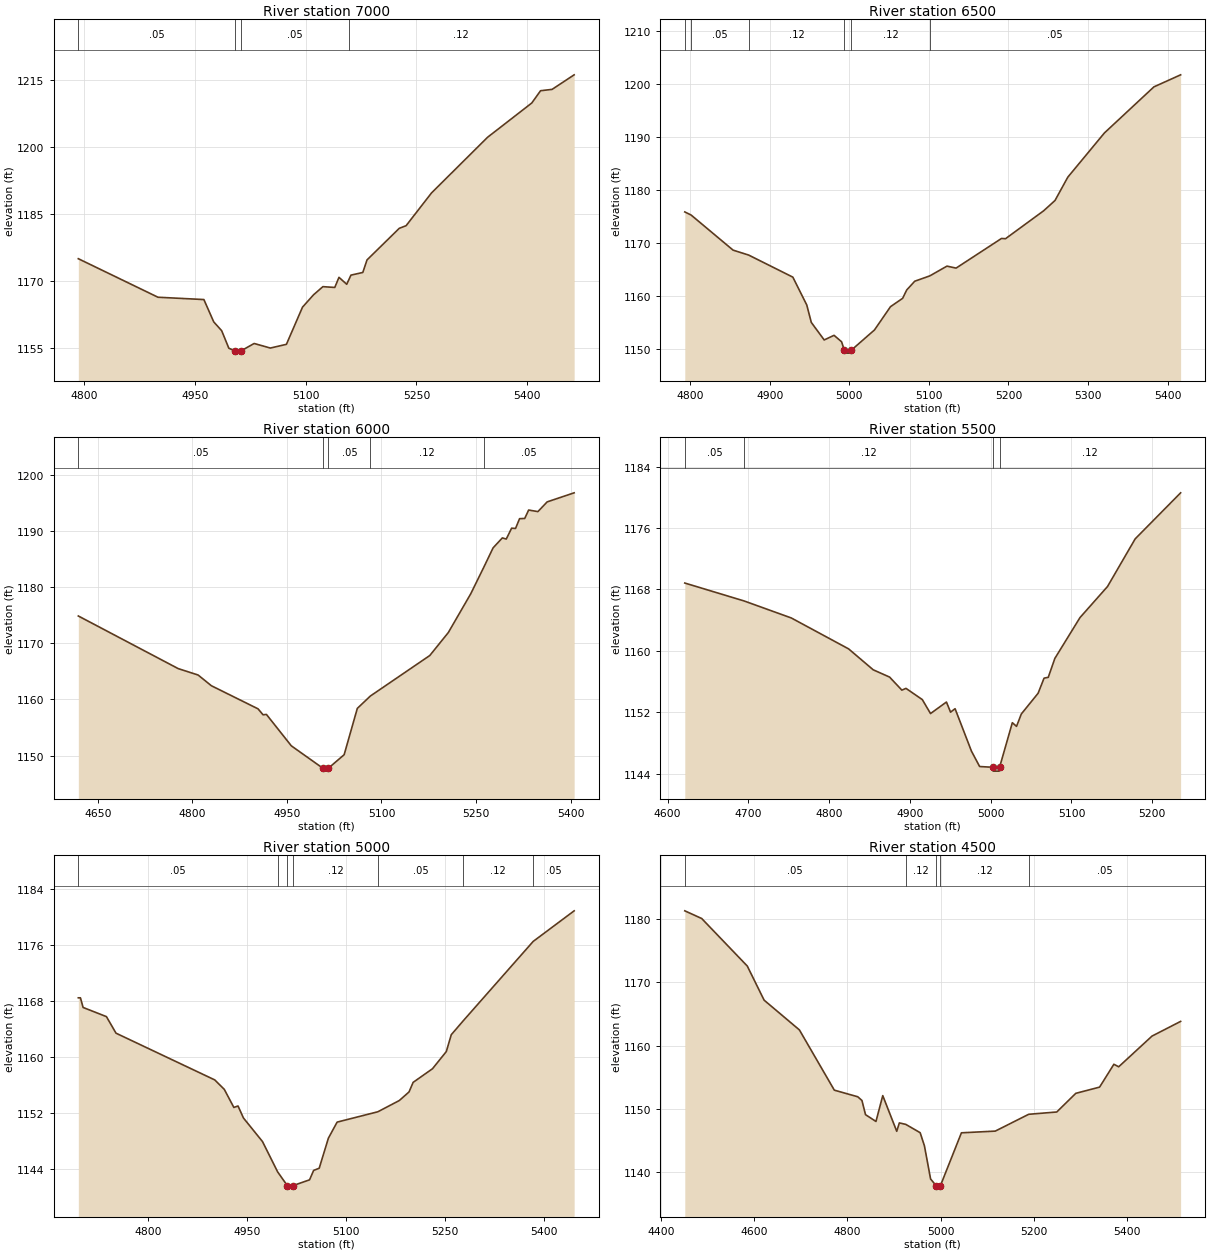
Type RM Length L Ch R = 1,7000,500,500,500
BEGIN DESCRIPTION:
HICKORY MT BRANCH 14.0
END DESCRIPTION:
XS GIS Cut Line= 3
      2808455.71     10213753.10      2808648.54     10213674.87
      2809055.67     10213453.12
#Sta/Elev= 30
  4791.9 1175.07  4899.8 1166.44  4962.0 1165.92  4975.3 1160.93  4986.1 1158.94
  4995.8 1155.02  5004.1 1154.42  5004.6 1153.92  5012.2 1154.42  5030.1 1156.08
  5052.0 1155.06  5073.8 1155.89  5095.6 1164.22  5110.6 1166.99  5123.2 1168.81
  5139.3 1168.63  5145.0 1170.90  5155.5 1169.34  5158.0 1170.24  5161.2 1171.39
  5177.3 1171.99  5183.0 1174.80  5226.7 1181.88  5235.9 1182.46  5270.4 1189.81
  5346.3 1202.27  5406.2 1209.95  5418.1 1212.70  5433.7 1213.00  5463.6 1216.26
#Mann=4,-1,0
  4791.9    0.05       0  5004.1    0.05       0  5012.2    0.05       0
  5158.0    0.12       0
Bank Sta=5004.1,5012.2
Exp/Cntr=0.3,0.1

Type RM Length L Ch R = 1,6500,500,500,500
BEGIN DESCRIPTION:
HICKORY MT BRANCH 13.0
END DESCRIPTION:
XS GIS Cut Line= 3
      2808455.72     10214253.09      2808644.50     10214168.65
      2809055.70     10214103.11
#Sta/Elev= 30
  4793.2 1175.87  4801.1 1175.29  4853.9 1168.68  4873.5 1167.75  4929.0 1163.60
  4946.5 1158.36  4952.2 1155.08  4968.4 1151.78  4980.8 1152.65  4990.3 1151.43
  4993.8 1149.80  4994.3 1149.30  5001.6 1149.30  5002.1 1149.80  5031.6 1153.66
  5051.8 1158.05  5067.0 1159.61  5072.1 1161.18  5082.2 1162.83  5101.2 1163.84
  5122.7 1165.67  5134.2 1165.30  5191.3 1170.88  5196.3 1170.83  5244.2 1176.08
  5258.5 1178.02  5274.6 1182.41  5320.6 1190.73  5382.8 1199.40  5416.4 1201.67
#Mann=6,-1,0
  4793.2    0.12       0  4801.1    0.05       0  4873.5    0.12       0
  4993.8    0.07       0  5002.1    0.12       0  5101.2    0.05       0
Bank Sta=4993.8,5002.1
Exp/Cntr=0.3,0.1

Type RM Length L Ch R = 1,6000,500,500,500
BEGIN DESCRIPTION:
HICKORY MT BRANCH 12.0
END DESCRIPTION:
XS GIS Cut Line= 3
      2808505.71     10214703.10      2808866.45     10214580.82
      2809105.66     10214253.14
#Sta/Elev= 30
  4619.1 1174.84  4777.5 1165.48  4809.1 1164.34  4830.2 1162.43  4904.2 1158.32
  4912.2 1157.26  4917.5 1157.33  4957.0 1151.74  5007.3 1147.74  5007.8 1147.24
  5015.1 1147.24  5015.6 1147.74  5040.8 1150.16  5061.7 1158.40  5082.4 1160.60
  5176.7 1167.81  5206.1 1171.90  5241.6 1178.78  5263.0 1183.66  5277.1 1186.96
  5291.8 1188.73  5298.0 1188.53  5306.5 1190.46  5312.7 1190.41  5319.1 1192.15
  5327.3 1192.19  5333.5 1193.69  5348.2 1193.41  5362.9 1195.14  5405.7 1196.75
#Mann=5,-1,0
  4619.1    0.05       0  5007.3    0.05       0  5015.6    0.05       0
  5082.4    0.12       0  5263.0    0.05       0
Bank Sta=5007.3,5015.6
Exp/Cntr=0.3,0.1

Type RM Length L Ch R = 1,5500,500,500,500
BEGIN DESCRIPTION:
HICKORY MT BRANCH 11.0
END DESCRIPTION:
XS GIS Cut Line= 3
      2808655.69     10214953.11      2809029.15     10215016.53
      2809255.64     10214953.12
#Sta/Elev= 30
  4621.2 1168.83  4694.8 1166.49  4753.1 1164.28  4824.1 1160.25  4854.5 1157.53
  4874.8 1156.58  4890.0 1154.88  4895.1 1155.11  4915.3 1153.65  4925.5 1151.83
  4945.2 1153.33  4950.3 1152.01  4955.9 1152.46  4976.2 1146.93  4986.3 1144.93
  5002.6 1144.83  5003.1 1144.33  5010.5 1144.33  5011.0 1144.83  5026.8 1150.64
  5032.0 1150.16  5037.9 1151.77  5058.7 1154.47  5066.1 1156.44  5071.3 1156.55
  5079.5 1159.02  5110.6 1164.33  5144.7 1168.38  5178.9 1174.58  5235.2 1180.58
#Mann=4,-1,0
  4621.2    0.05       0  4694.8    0.12       0  5002.6    0.07       0
  5011.0    0.12       0
Bank Sta=5002.6,5011
Exp/Cntr=0.3,0.1

Type RM Length L Ch R = 1,5000,500,500,500
BEGIN DESCRIPTION:
HICKORY MT BRANCH 10.0
END DESCRIPTION:
XS GIS Cut Line= 3
      2808855.68     10215753.11      2809042.85     10215512.17
      2809305.70     10215153.09
#Sta/Elev= 30
  4694.9 1168.46  4698.1 1168.46  4702.1 1167.08  4737.4 1165.77  4751.9 1163.40
  4901.3 1156.71  4915.7 1155.36  4930.2 1152.77  4936.5 1152.98  4944.7 1151.26
  4973.5 1147.89  4996.4 1143.55  5011.1 1141.58  5011.6 1141.08  5019.6 1141.58
  5044.7 1142.41  5050.9 1143.76  5059.3 1144.07  5073.2 1148.37  5086.4 1150.67
  5148.0 1152.15  5180.5 1153.76  5195.2 1154.99  5201.4 1156.36  5230.7 1158.31
  5251.6 1160.77  5259.1 1163.18  5277.0 1165.15  5383.0 1176.53  5445.0 1180.91
#Mann=7,-1,0
  4694.9    0.05       0  4996.4    0.12       0  5011.1    0.07       0
  5019.6    0.12       0  5148.0    0.05       0  5277.0    0.12       0
  5383.0    0.05       0
Bank Sta=5011.1,5019.6
Exp/Cntr=0.3,0.1

Type RM Length L Ch R = 1,4500,500,500,500
BEGIN DESCRIPTION:
HICKORY MT BRANCH 9.0
END DESCRIPTION:
XS GIS Cut Line= 3
      2808855.70     10216153.10      2809346.70     10215906.82
      2809455.69     10215403.08
#Sta/Elev= 30
  4450.7 1181.22  4487.0 1180.01  4584.9 1172.52  4621.0 1167.15  4696.8 1162.46
  4771.8 1152.97  4822.1 1151.93  4831.1 1151.34  4838.8 1149.11  4861.2 1148.04
  4875.8 1152.11  4905.8 1146.49  4911.4 1147.81  4925.2 1147.58  4956.1 1146.27
  4965.3 1144.19  4978.5 1138.98  4990.9 1137.88  4991.4 1137.38  4999.4 1137.88
  5044.7 1146.25  5117.4 1146.52  5189.2 1149.17  5249.4 1149.53  5290.3 1152.47
  5341.4 1153.45  5372.1 1157.05  5382.4 1156.65  5454.0 1161.49  5515.4 1163.80
#Mann=5,-1,0
  4450.7    0.05       0  4925.2    0.12       0  4990.9    0.07       0
  4999.4    0.12       0  5189.2    0.05       0
Bank Sta=4990.9,4999.4
Exp/Cntr=0.3,0.1

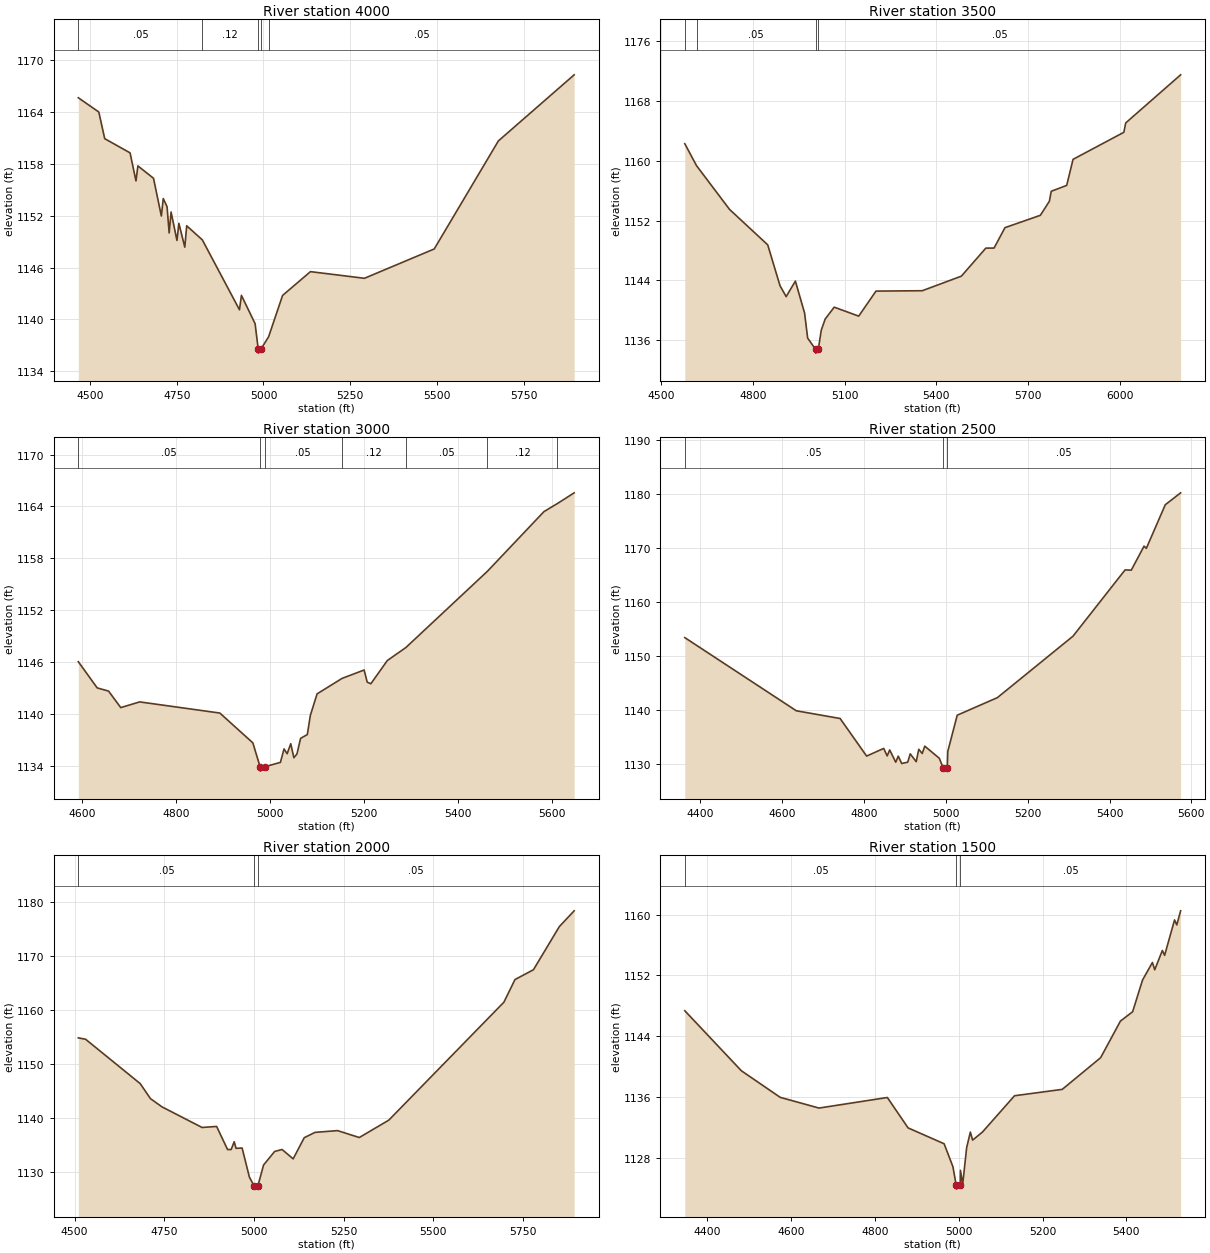
Type RM Length L Ch R = 1,4000,500,500,500
BEGIN DESCRIPTION:
HICKORY MT BRANCH 8.0
END DESCRIPTION:
XS GIS Cut Line= 3
      2809255.69     10216453.11      2809735.47     10216219.12
      2809505.68     10215353.09
#Sta/Elev= 30
  4466.2 1165.63  4525.3 1163.98  4542.3 1160.90  4615.4 1159.26  4632.4 1156.02
  4638.0 1157.75  4683.0 1156.32  4705.6 1151.96  4711.1 1153.98  4722.1 1153.03
  4728.1 1150.01  4733.7 1152.42  4750.6 1149.14  4756.2 1151.11  4773.2 1148.36
  4778.7 1150.83  4823.8 1149.20  4930.9 1141.12  4936.5 1142.79  4976.0 1139.51
  4984.8 1136.61  4985.3 1136.11  4993.4 1136.61  5014.9 1138.00  5055.2 1142.78
  5135.6 1145.53  5291.2 1144.76  5492.5 1148.15  5677.5 1160.64  5896.0 1168.28
#Mann=5,-1,0
  4466.2    0.05       0  4823.8    0.12       0  4984.8    0.07       0
  4993.4    0.12       0  5014.9    0.05       0
Bank Sta=4984.8,4993.4
Exp/Cntr=0.3,0.1

Type RM Length L Ch R = 1,3500,500,500,500
BEGIN DESCRIPTION:
HICKORY MT BRANCH 7.0
END DESCRIPTION:
XS GIS Cut Line= 3
      2810155.68     10216653.11      2810198.77     10216232.61
      2809505.69     10215253.12
#Sta/Elev= 30
  4577.3 1162.28  4615.8 1159.34  4723.8 1153.49  4848.7 1148.75  4888.9 1143.28
  4909.0 1141.82  4939.2 1143.90  4969.3 1139.63  4979.4 1136.27  5005.4 1134.76
  5005.9 1134.26  5014.2 1134.76  5023.9 1137.33  5036.8 1138.83  5066.3 1140.41
  5146.4 1139.21  5203.0 1142.56  5354.4 1142.61  5482.4 1144.56  5562.4 1148.31
  5589.4 1148.32  5625.1 1151.05  5740.8 1152.70  5770.4 1154.58  5776.5 1155.92
  5827.0 1156.70  5847.9 1160.19  6014.1 1163.81  6020.2 1165.06  6199.9 1171.50
#Mann=4,-1,0
  4577.3    0.12       0  4615.8    0.05       0  5005.4    0.05       0
  5014.2    0.05       0
Bank Sta=5005.4,5014.2
Exp/Cntr=0.3,0.1

Type RM Length L Ch R = 1,3000,500,500,500
BEGIN DESCRIPTION:
HICKORY MT BRANCH 6.0
END DESCRIPTION:
XS GIS Cut Line= 3
      2810455.69     10216253.08      2810487.73     10215847.14
      2810905.68     10215353.12
#Sta/Elev= 30
  4592.8 1146.04  4632.9 1143.01  4657.1 1142.64  4683.0 1140.73  4723.2 1141.39
  4893.7 1140.10  4963.9 1136.65  4979.3 1133.88  4979.8 1133.38  4988.7 1133.88
  5022.5 1134.39  5030.2 1135.95  5036.8 1135.39  5044.5 1136.55  5051.1 1134.93
  5057.7 1135.37  5065.4 1137.17  5079.7 1137.61  5086.2 1139.84  5100.5 1142.32
  5153.6 1144.11  5200.5 1145.08  5207.1 1143.67  5214.8 1143.49  5249.9 1146.18
  5289.3 1147.68  5462.6 1156.50  5582.8 1163.40  5611.5 1164.34  5647.1 1165.58
#Mann=7,-1,0
  4592.8    0.05       0  4979.3    0.05       0  4988.7    0.05       0
  5153.6    0.12       0  5289.3    0.05       0  5462.6    0.12       0
  5611.5    0.05       0
Bank Sta=4979.3,4988.7
Exp/Cntr=0.3,0.1

Type RM Length L Ch R = 1,2500,500,500,500
BEGIN DESCRIPTION:
HICKORY MT BRANCH 5.0
END DESCRIPTION:
XS GIS Cut Line= 3
      2810405.65     10216353.14      2810920.65     10215976.55
      2811155.69     10215453.09
#Sta/Elev= 30
  4362.0 1153.41  4634.6 1139.84  4741.6 1138.41  4806.4 1131.44  4848.1 1132.86
  4856.6 1131.47  4862.8 1132.58  4877.5 1130.31  4883.7 1131.43  4892.1 1130.06
  4906.8 1130.31  4913.0 1131.85  4927.6 1130.40  4933.8 1132.70  4942.3 1131.92
  4948.5 1133.28  4984.0 1131.04  4994.0 1129.15  4994.5 1128.65  5003.4 1129.15
  5004.7 1132.29  5027.8 1139.02  5126.0 1142.28  5310.7 1153.67  5438.1 1165.97
  5453.2 1165.92  5484.5 1170.38  5490.0 1169.96  5536.3 1178.05  5573.8 1180.26
#Mann=3,-1,0
  4362.0    0.05       0  4994.0    0.03       0  5003.4    0.05       0
Bank Sta=4994,5003.4
Exp/Cntr=0.3,0.1

Type RM Length L Ch R = 1,2000,500,500,500
BEGIN DESCRIPTION:
HICKORY MT BRANCH 4.0
END DESCRIPTION:
XS GIS Cut Line= 3
      2810505.65     10216403.12      2810988.11     10216319.25
      2811205.70     10215453.06
#Sta/Elev= 30
  4510.3 1154.82  4530.6 1154.56  4682.9 1146.34  4711.5 1143.56  4743.8 1142.03
  4855.4 1138.22  4896.0 1138.41  4926.5 1134.13  4936.6 1134.14  4945.0 1135.58
  4950.1 1134.36  4967.1 1134.41  4987.4 1129.03  5001.1 1127.30  5001.6 1126.80
  5010.6 1127.30  5027.0 1131.28  5057.9 1133.78  5078.5 1134.14  5109.4 1132.41
  5140.4 1136.33  5170.4 1137.31  5233.2 1137.64  5293.9 1136.36  5376.2 1139.58
  5697.1 1161.42  5728.1 1165.62  5779.6 1167.44  5851.8 1175.43  5893.1 1178.35
#Mann=3,-1,0
  4510.3    0.05       0  5001.1    0.05       0  5010.6    0.05       0
Bank Sta=5001.1,5010.6
Exp/Cntr=0.3,0.1

Type RM Length L Ch R = 1,1500,500,500,500
BEGIN DESCRIPTION:
HICKORY MT BRANCH 3.0
END DESCRIPTION:
XS GIS Cut Line= 3
      2810955.67     10216703.12      2811462.80     10216290.32
      2811255.69     10215803.12
#Sta/Elev= 30
  4346.1 1147.34  4481.1 1139.44  4573.8 1135.94  4666.4 1134.53  4829.5 1135.92
  4879.0 1131.92  4965.0 1129.83  4986.0 1126.81  4993.9 1124.36  4994.4 1123.86
  5003.4 1124.36  5003.9 1126.34  5009.3 1124.50  5018.7 1129.30  5027.6 1131.37
  5033.0 1130.31  5056.6 1131.38  5133.0 1136.15  5246.9 1136.99  5338.5 1141.16
  5385.8 1145.98  5414.9 1147.21  5438.5 1151.38  5462.1 1153.69  5467.6 1152.73
  5485.8 1155.27  5491.2 1154.63  5514.9 1159.29  5520.3 1158.64  5529.4 1160.49
#Mann=3,-1,0
  4346.1    0.05       0  4993.9    0.05       0  5003.4    0.05       0
Bank Sta=4993.9,5003.4
Exp/Cntr=0.3,0.1

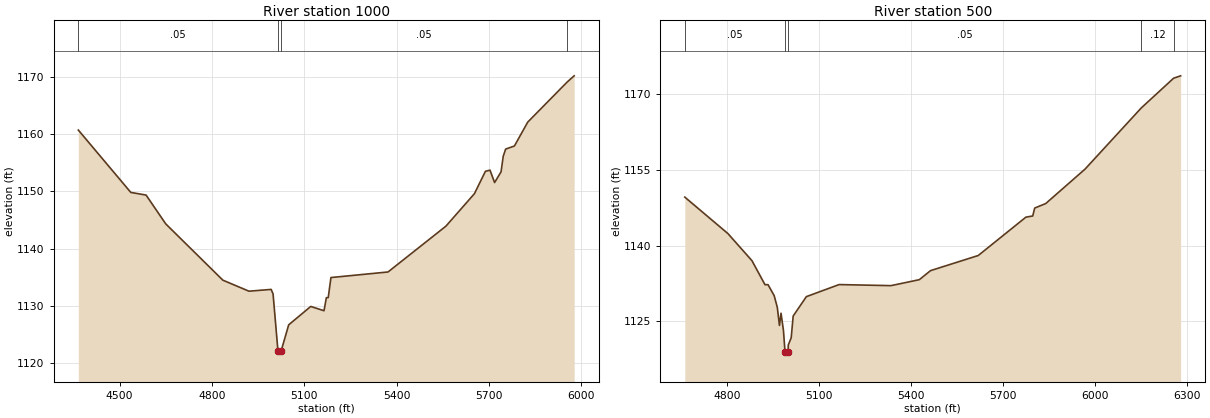
Type RM Length L Ch R = 1,1000,500,500,500
BEGIN DESCRIPTION:
HICKORY MT BRANCH 2.0
END DESCRIPTION:
XS GIS Cut Line= 3
      2811005.67     10217153.12      2811500.36     10216756.44
      2812305.69     10216203.11
#Sta/Elev= 30
  4365.9 1160.67  4536.4 1149.79  4586.0 1149.33  4650.0 1144.30  4835.6 1134.48
  4920.4 1132.56  4992.5 1132.87  4998.7 1132.08  5014.7 1122.08  5015.2 1121.58
  5024.6 1122.08  5049.5 1126.69  5121.2 1129.90  5164.2 1129.15  5171.9 1131.42
  5178.0 1131.45  5186.8 1134.94  5372.2 1135.91  5560.3 1143.90  5653.0 1149.57
  5688.8 1153.48  5703.7 1153.67  5718.6 1151.51  5739.6 1153.39  5746.6 1156.09
  5754.5 1157.35  5783.0 1157.89  5826.2 1162.05  5953.9 1169.02  5977.1 1170.13
#Mann=4,-1,0
  4365.9    0.05       0  5014.7    0.03       0  5024.6    0.05       0
  5953.9    0.12       0
Bank Sta=5014.7,5024.6
Exp/Cntr=0.3,0.1

Type RM Length L Ch R = 1,500,0,0,0
BEGIN DESCRIPTION:
HICKORY MT BRANCH 1.0
END DESCRIPTION:
XS GIS Cut Line= 3
      2811255.69     10217153.11      2811592.15     10217191.20
      2812405.68     10216203.12
#Sta/Elev= 30
  4661.4 1149.61  4802.3 1142.38  4880.7 1137.01  4923.1 1132.26  4933.1 1132.26
  4953.2 1130.08  4963.3 1127.79  4970.4 1124.18  4975.5 1126.61  4983.4 1123.21
  4988.5 1119.00  4989.0 1118.50  4998.5 1119.00  4999.3 1120.32  5008.7 1121.73
  5015.2 1126.05  5058.2 1129.89  5165.1 1132.28  5334.4 1132.07  5427.0 1133.25
  5463.5 1135.04  5619.3 1138.04  5774.9 1145.64  5797.1 1145.87  5803.6 1147.44
  5839.5 1148.33  5967.8 1155.15  6151.5 1167.28  6257.1 1173.17  6279.9 1173.64
#Mann=5,-1,0
  4661.4    0.05       0  4988.5    0.05       0  4998.5    0.05       0
  6151.5    0.12       0  6257.1    0.05       0
Bank Sta=4988.5,4998.5
Exp/Cntr=0.3,0.1

Chan Stop Cuts=-1