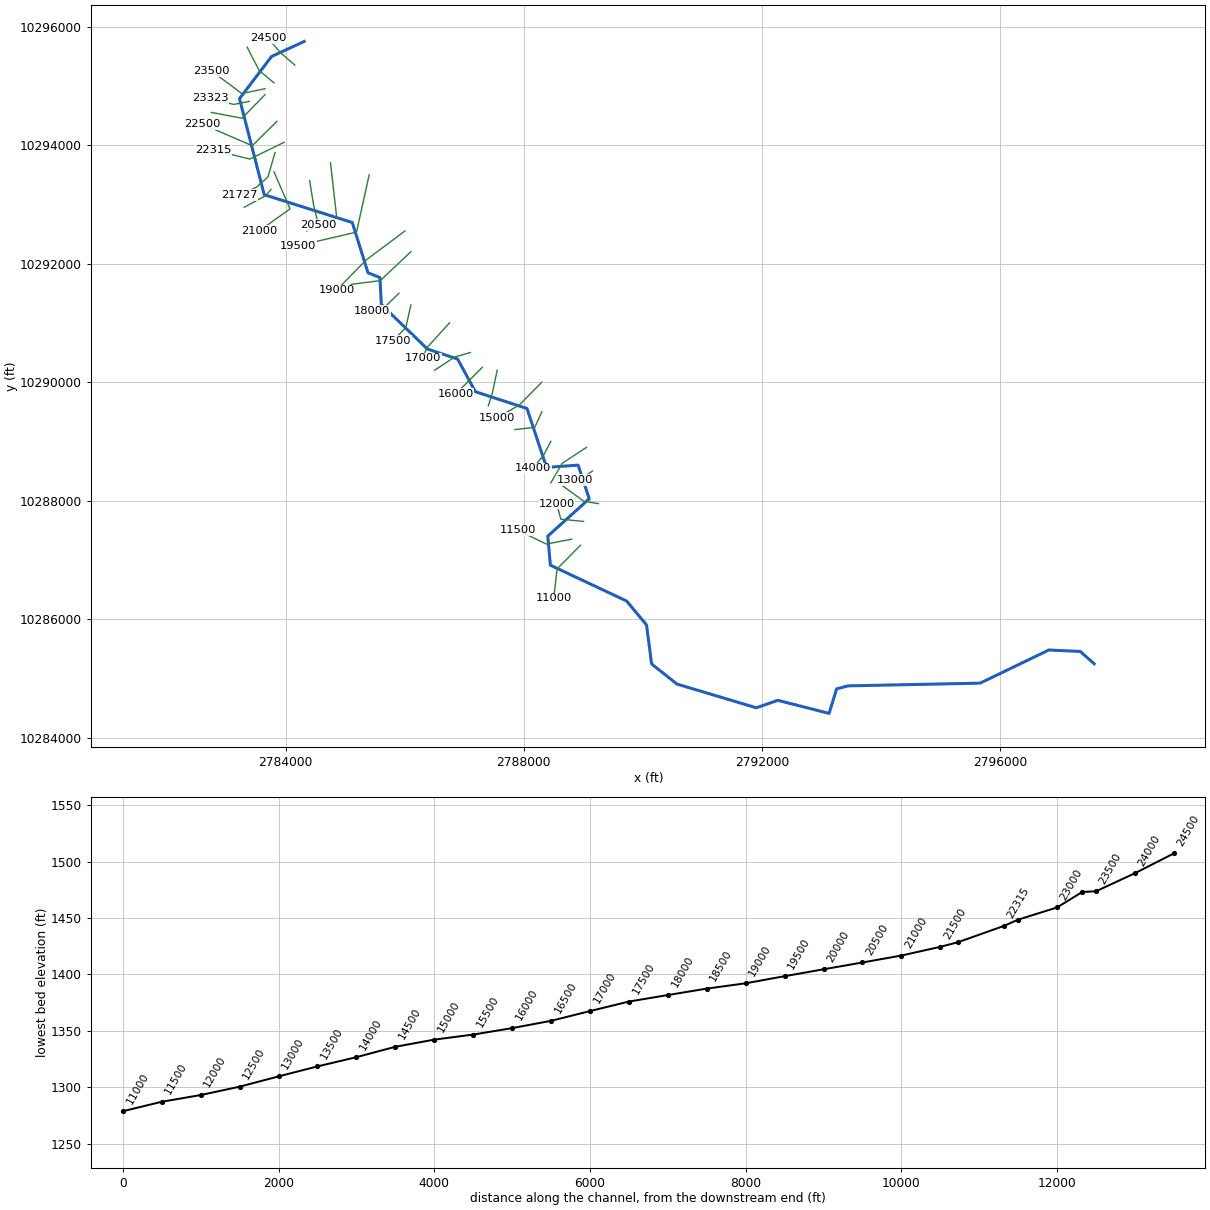
--- MAGILL CREEK.prj (project) ---

Proj Title=MAGILL CREEK Base Level Engineering
Current Plan=p01
Default Exp/Contr=0.3,0.1
English Units
Geom File=g01
Flow File=f01
Plan File=p01
Y Axis Title=Elevation
X Axis Title(PF)=Main Channel Distance
X Axis Title(XS)=Station
BEGIN DESCRIPTION:
MAGILL CREEK
END DESCRIPTION:
DSS Export Rating Curves= 0
DSS Export Rating Curve Sorted= 0
DSS Export Volume Flow Curves= 0
DXF OffsetX= 0
DXF OffsetY= 0
DXF ScaleX= 1
DXF ScaleY= 10

--- MAGILL CREEK.p01 (plan) ---

Plan Title=Multiple Run
Short Identifier=Multiple
Geom File=g01
Flow File=f01
Subcritical Flow
K Sum by GR= 0
Std Step Tol= 0.01
Critical Tol= 0.01
Num of Std Step Trials= 20
Max Error Tol= 0.3
Flow Tol Ratio= 0.001
Split Flow NTrial= 30
Split Flow Tol= 0.02
Split Flow Ratio= 0.02
Log Output Level= 0
Friction Slope Method= 1
Unsteady Friction Slope Method= 2
Unsteady Bridges Friction Slope Method= 1
Parabolic Critical Depth
Global Vel Dist=  1 , 1 , 1
Global Log Level= 0
CheckData=True
Encroach Param= -1, 0, 0, 0
BEGIN DESCRIPTION:
Multiple Run
END DESCRIPTION:

--- MAGILL CREEK.f01 (steady flow) ---

Flow Title=Multiple
Number of Profiles=7
Profile Names=10-year,25-year,50-year,1pct_min,100-year,1pct_plu,500-year
River Rch & RM= MAGILL CREEK,Reach-1,24500
     417     672    1261     897    1749    3412    2511
River Rch & RM= MAGILL CREEK,Reach-1,15500
     763    1285    2417    1752    3420    6676    4901
River Rch & RM= MAGILL CREEK,Reach-1,8000
    1024    1760    3291    2047    4693   10757    6694
River Rch & RM= MAGILL CREEK,Reach-1,3500
    1200    2086    3839    2284    5493   13206    7813
Boundary for River Rch & Prof#=MAGILL CREEK,Reach-1,1
Up Type=0
Dn Type=3
Dn Slope=0.005
Boundary for River Rch & Prof#=MAGILL CREEK,Reach-1,2
Up Type=0
Dn Type=3
Dn Slope=0.005
Boundary for River Rch & Prof#=MAGILL CREEK,Reach-1,3
Up Type=0
Dn Type=3
Dn Slope=0.005
Boundary for River Rch & Prof#=MAGILL CREEK,Reach-1,4
Up Type=0
Dn Type=3
Dn Slope=0.005
Boundary for River Rch & Prof#=MAGILL CREEK,Reach-1,5
Up Type=0
Dn Type=3
Dn Slope=0.005
Boundary for River Rch & Prof#=MAGILL CREEK,Reach-1,6
Up Type=0
Dn Type=3
Dn Slope=0.005
Boundary for River Rch & Prof#=MAGILL CREEK,Reach-1,7
Up Type=0
Dn Type=3
Dn Slope=0.005

--- MAGILL CREEK.g01 (geometry) ---

Geom Title=Existing Conditions
Program Version=4.10

River Reach=MAGILL CREEK    ,Reach-1
Reach XY= 30
      2784312.75       10295750.        2783766.       10295497.
      2783226.75       10294786.      2783642.25       10293165.
      2785121.25       10292696.      2785385.75       10291847.
        2785585.       10291768.      2785609.75       10291312.
      2786381.75       10290563.        2786891.       10290392.
        2787189.       10289842.      2788056.25       10289558.
        2788384.       10288565.      2788915.25       10288603.
      2789101.75       10288035.       2788405.5       10287406.
      2788448.75       10286915.        2789730.       10286310.
       2790064.5       10285906.      2790148.75       10285249.
      2790575.75       10284909.      2791909.25       10284509.
      2792267.75       10284635.      2793131.25       10284415.
      2793256.25       10284828.      2793447.25       10284879.
       2795667.5       10284925.        2796822.       10285484.
      2797348.25       10285460.       2797583.5       10285252.

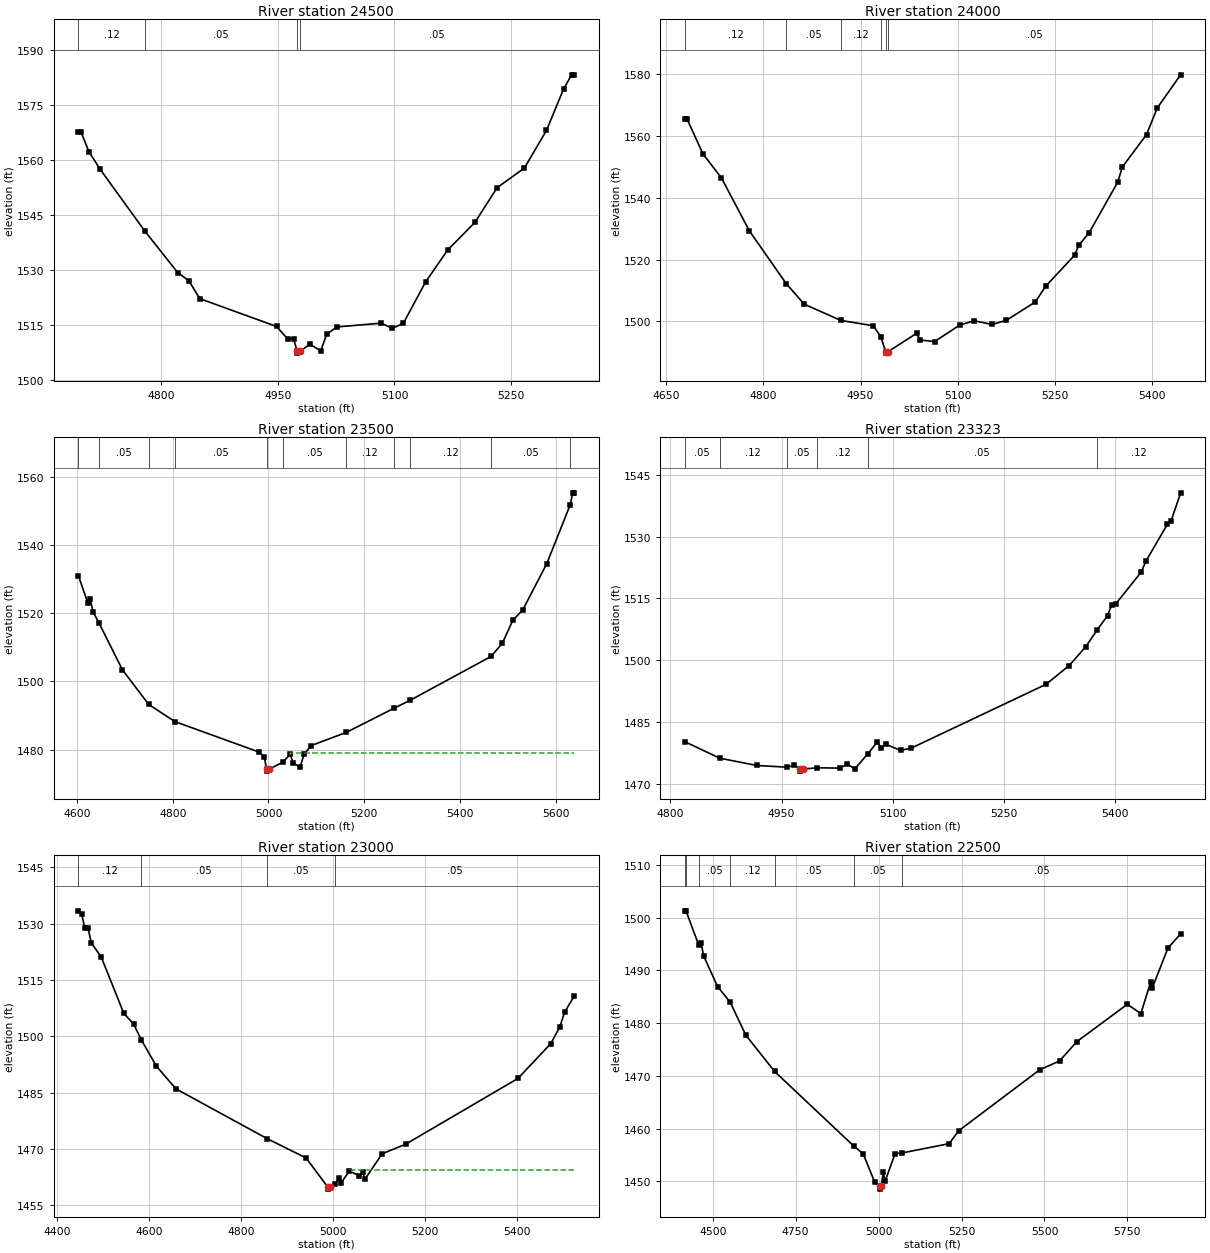
Type RM Length L Ch R = 1 ,24500   ,500,500,500
BEGIN DESCRIPTION:
MAGILL CREEK 49.0
END DESCRIPTION:
XS GIS Cut Line= 3
      2784155.66     10295353.13      2783923.52     10295553.57
      2783705.71     10295803.08
#Sta/Elev= 30
  4693.3 1567.74  4696.6 1567.74    4707 1562.25  4721.3  1557.5  4778.9 1540.57
  4821.1 1529.26  4835.3 1527.06  4849.6 1522.12  4948.3 1514.52  4962.6 1511.11
  4970.2 1511.21  4974.8 1507.74  4975.1 1507.24  4978.8 1507.74  4991.1  1509.7
  5005.2 1507.84  5012.7  1512.4    5026  1514.4    5083 1515.43  5097.2 1514.01
  5111.5  1515.4    5140 1526.67  5168.4  1535.4  5203.6 1542.99    5232 1552.43
  5267.2 1557.82  5295.6  1568.1  5317.5 1579.38  5327.9 1583.29  5331.2 1583.29
#Mann= 4 ,-1 , 0
  4693.3     .12       0  4778.9     .05       0  4974.8     .05       0
  4978.8     .05       0
Bank Sta=4974.8,4978.8
XS Rating Curve= 0 ,0
Exp/Cntr=0.3,0.1

Type RM Length L Ch R = 1 ,24000   ,500,500,500
BEGIN DESCRIPTION:
MAGILL CREEK 48.0
END DESCRIPTION:
XS GIS Cut Line= 3
      2783805.66     10295053.13      2783558.64     10295258.27
      2783355.71     10295653.07
#Sta/Elev= 30
  4678.9 1565.61  4682.1 1565.61  4706.9  1554.2  4735.5  1546.4  4778.5 1529.28
  4835.3 1512.22  4863.1 1505.55  4919.6 1500.28  4969.9 1498.55  4981.4 1494.96
  4988.8  1490.2  4989.1  1489.7  4992.8  1490.2  5036.4  1496.1    5042 1493.95
  5064.2 1493.43    5103 1498.77  5125.1 1500.18  5152.9 1498.99  5175.1 1500.32
  5219.5 1506.24    5236 1511.42  5280.4 1521.42  5286.5 1524.55  5302.6 1528.61
  5346.9 1545.06    5354 1549.97  5391.3 1560.44  5407.9 1569.07  5443.9 1579.78
#Mann= 6 ,-1 , 0
  4678.9     .12       0  4835.3     .05       0  4919.6     .12       0
  4981.4     .05       0  4988.8     .05       0  4992.8     .05       0
Bank Sta=4988.8,4992.8
XS Rating Curve= 0 ,0
Exp/Cntr=0.3,0.1

Type RM Length L Ch R = 1 ,23500   ,177,177,177
BEGIN DESCRIPTION:
MAGILL CREEK 47.0
END DESCRIPTION:
XS GIS Cut Line= 3
      2783655.69     10294953.11      2783267.18      10294871.4
      2782755.71      10295253.1
#Sta/Elev= 30
    4603 1531.11  4622.8 1523.04  4627.9 1524.17  4633.7 1520.43  4646.2 1517.14
    4695 1503.42    4750 1493.23  4804.6 1488.21  4981.1 1479.22  4991.3 1477.79
  4996.2 1474.16  4996.5 1473.66  5000.2 1474.16  5030.5 1476.32  5045.1  1478.6
  5051.8 1476.01  5065.9 1474.85  5074.3 1478.57  5088.9 1481.15  5162.6 1485.04
  5261.4 1492.09  5295.6 1494.45    5465 1507.37  5488.5 1511.28    5510 1517.93
  5530.9 1521.02  5580.9 1534.55    5630 1551.89  5635.1 1555.39  5638.2 1555.39
#Mann= 11 ,-1 , 0
    4603     .12       0  4646.2     .05       0    4750     .12       0
  4804.6     .05       0  4996.2     .05       0  5030.5     .05       0
  5162.6     .12       0  5261.4     .05       0  5295.6     .12       0
    5465     .05       0    5630     .12       0
#XS Ineff= 2 , 0
                         5045.77         1478.95
Permanent Ineff=
       F       F
Bank Sta=4996.2,5000.2
XS Rating Curve= 0 ,0
Exp/Cntr=0.3,0.1

Type RM Length L Ch R = 1 ,23323   ,323,323,323
BEGIN DESCRIPTION:
Mapping XS 19c45dc3
END DESCRIPTION:
XS GIS Cut Line= 3
      2783390.91     10294740.01       2783130.5     10294687.92
      2782740.31     10294791.97
#Sta/Elev= 30
  4819.4  1480.2  4866.4  1476.2  4916.5 1474.42  4957.3 1474.01  4967.5 1474.42
  4975.3 1473.55  4975.6 1473.05  4979.3 1473.55  4998.1 1473.86  5028.3 1473.78
  5038.9 1474.71  5049.1 1473.61  5066.2 1477.21  5079.3 1480.11  5084.4 1478.72
  5090.4 1479.58  5110.7 1478.09  5125.3 1478.65  5307.3 1494.14  5338.3 1498.68
  5360.8 1503.28  5375.8 1507.24  5390.1  1510.8  5395.7  1513.4  5400.9 1513.58
  5435.8 1521.41  5441.8 1523.97  5470.8 1532.94  5475.9 1533.79  5488.8 1540.61
#Mann= 6 ,-1 , 0
  4819.4     .05       0  4866.4     .12       0  4957.3     .05       0
  4998.1     .12       0  5066.2     .05       0  5375.8     .12       0
Bank Sta=4975.3,4979.3
XS Rating Curve= 0 ,0
Exp/Cntr=0.3,0.1

Type RM Length L Ch R = 1 ,23000   ,500,500,500
BEGIN DESCRIPTION:
MAGILL CREEK 46.0
END DESCRIPTION:
XS GIS Cut Line= 3
      2783655.68     10294853.11      2783270.53     10294455.45
      2782755.71     10294553.11
#Sta/Elev= 30
  4446.4 1533.43  4453.5 1532.67  4460.4 1528.86  4467.6 1528.83  4474.6 1524.87
  4495.9 1521.21  4545.3 1506.12  4566.6 1503.29  4583.3 1499.08  4616.1 1492.06
  4658.5 1486.04  4856.6 1472.79  4941.4 1467.64  4988.8 1459.84  4989.1 1459.34
  4992.8 1459.84    5005 1460.68  5012.2 1462.33  5017.2 1460.93  5035.5 1464.19
  5055.8 1462.96  5064.4 1463.86  5069.5 1462.03  5106.7 1468.76  5157.6 1471.29
  5401.9 1488.81  5473.1 1498.07  5492.8 1502.52  5503.7 1506.58    5524 1510.66
#Mann= 4 ,-1 , 0
  4446.4     .12       0  4583.3     .05       0  4856.6     .05       0
    5005     .05       0
#XS Ineff= 2 , 0
                         5041.38         1464.46
Permanent Ineff=
       F       F
Bank Sta=4988.8,4992.8
XS Rating Curve= 0 ,0
Exp/Cntr=0.3,0.1

Type RM Length L Ch R = 1 ,22500   ,185,185,185
BEGIN DESCRIPTION:
MAGILL CREEK 45.0
END DESCRIPTION:
XS GIS Cut Line= 3
      2783855.71     10294403.14      2783441.32      10293991.5
       2782605.7     10294353.11
#Sta/Elev= 30
  4415.9 1501.32  4419.6 1501.31  4458.3 1494.75  4465.4 1495.14  4472.5 1492.79
  4514.9 1486.94  4553.1 1483.94  4599.8 1477.74  4686.6 1470.84    4925 1456.71
  4953.3 1455.24  4988.7  1449.8  5004.1 1449.02  5004.4 1448.52  5008.1 1449.02
  5014.1 1451.82  5019.6    1450  5049.7 1455.26    5072  1455.4  5212.9 1457.15
  5241.8 1459.61  5485.6 1471.16  5545.5 1472.84  5597.9 1476.52  5749.7 1483.58
  5790.7 1481.83  5820.1 1487.79  5825.6 1486.77  5872.6  1494.3  5910.5 1496.94
#Mann= 7 ,-1 , 0
  4415.9     .05       0  4419.6     .12       0  4458.3     .05       0
  4553.1     .12       0  4686.6     .05       0    4925     .05       0
    5072     .05       0
Bank Sta=5004.1,5008.1
XS Rating Curve= 0 ,0
Exp/Cntr=0.3,0.1

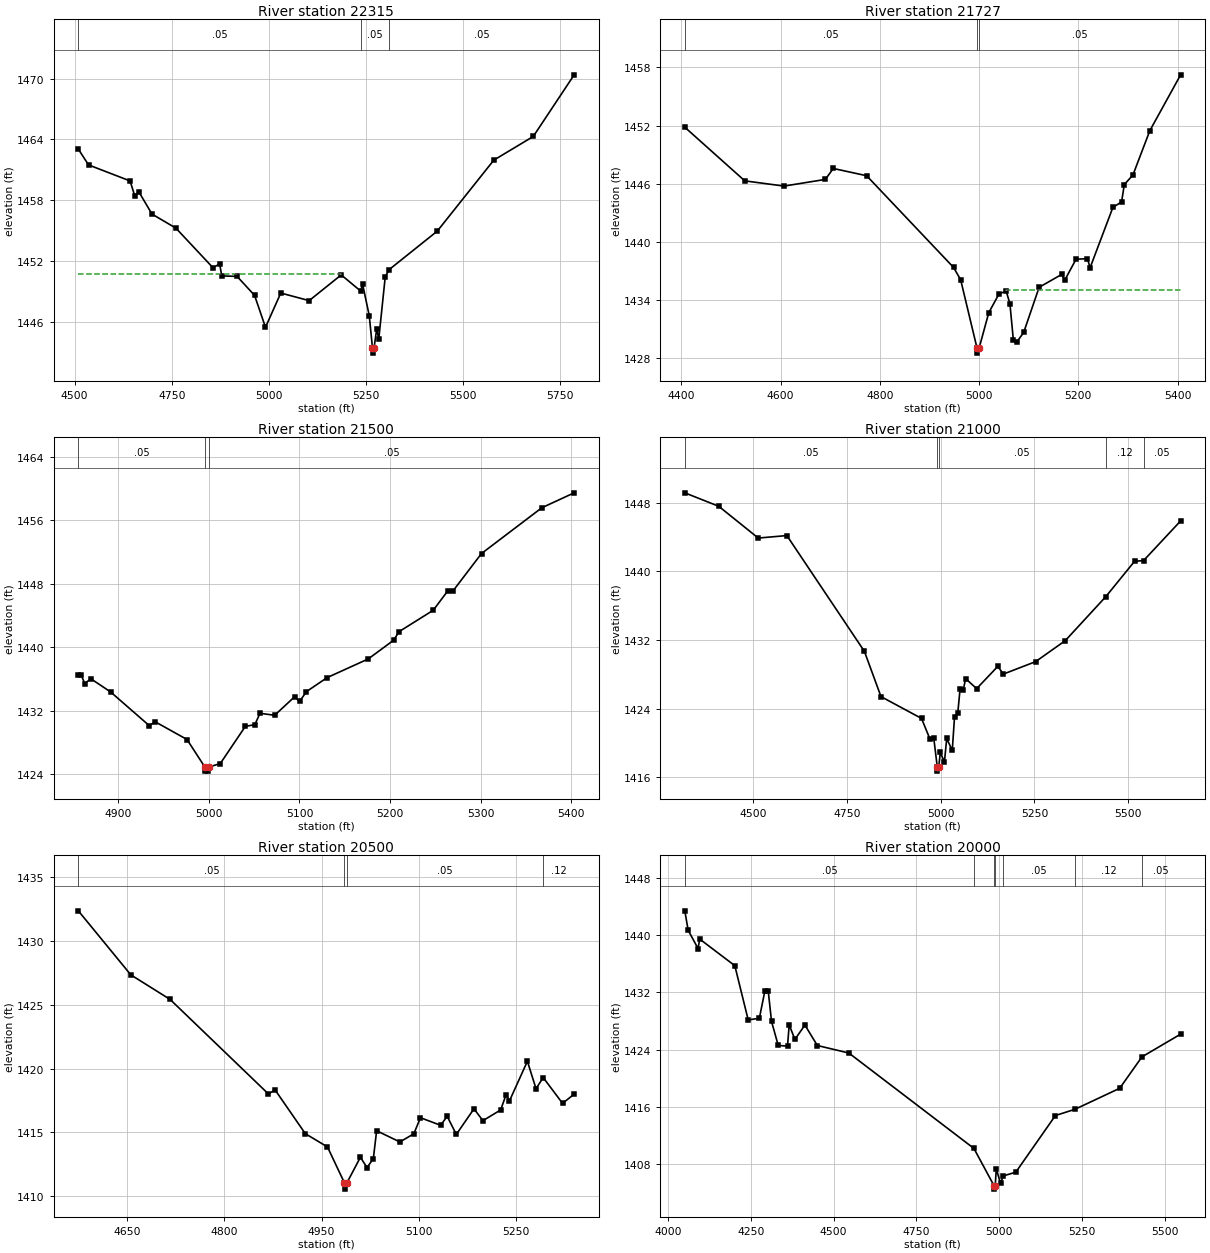
Type RM Length L Ch R = 1 ,22315   ,588,588,588
BEGIN DESCRIPTION:
Mapping XS 5e9853bd
END DESCRIPTION:
XS GIS Cut Line= 3
       2783975.9      10294048.9      2783400.82     10293766.79
      2782783.52     10293918.41
#Sta/Elev= 30
  4509.4 1463.05  4535.7 1461.49  4642.6 1459.91  4654.4 1458.46  4665.1 1458.84
    4699 1456.64  4760.6 1455.25  4856.1 1451.34  4873.1 1451.73  4878.6 1450.54
    4918 1450.49    4963 1448.62  4991.1 1445.47  5030.5 1448.85  5103.5  1448.1
  5186.1 1450.64  5235.9 1449.05  5241.1 1449.71  5258.2 1446.62  5266.5 1443.42
  5266.8 1442.92  5270.5 1443.42  5277.5 1445.35  5282.6 1444.28  5299.4 1450.47
  5309.7 1451.17  5433.3 1454.96  5578.7 1461.96  5680.4  1464.3  5785.6 1470.38
#Mann= 3 ,-1 , 0
  4509.4     .05       0  5235.9     .05       0  5309.7     .05       0
#XS Ineff= 2 , 0
         5185.58 1450.68
Permanent Ineff=
       F       F
Bank Sta=5266.5,5270.5
XS Rating Curve= 0 ,0
Exp/Cntr=0.3,0.1

Type RM Length L Ch R = 1 ,21727   ,227,227,227
BEGIN DESCRIPTION:
Mapping XS d86a44e0
END DESCRIPTION:
XS GIS Cut Line= 4
      2783823.99     10293875.28      2783704.64     10293462.97
      2783509.33     10293289.36      2783228.91     10293159.94
#Sta/Elev= 30
  4406.8 1451.83  4527.7 1446.29  4606.9 1445.75  4690.1 1446.44  4706.1 1447.57
  4773.3 1446.82  4948.5 1437.35  4962.8 1436.08  4995.9    1429  4996.1  1428.5
  4999.9    1429  5019.6 1432.69  5040.5 1434.65  5054.7 1434.88  5062.1 1433.61
    5069 1429.88  5075.6 1429.62  5089.9 1430.64    5121  1435.3  5166.9 1436.64
  5172.4 1436.01  5195.4  1438.2  5218.3 1438.25  5223.8 1437.33  5269.7 1443.55
  5287.2 1444.12  5292.7 1445.91  5310.1  1446.9  5344.1 1451.47  5406.2 1457.24
#Mann= 3 ,-1 , 0
  4406.8     .05       0  4995.9     .05       0  4999.9     .05       0
#XS Ineff= 2 , 0
                         5054.55         1434.98
Permanent Ineff=
       F       F
Bank Sta=4995.9,4999.9
XS Rating Curve= 0 ,0
Exp/Cntr=0.3,0.1

Type RM Length L Ch R = 1 ,21500   ,500,500,500
BEGIN DESCRIPTION:
MAGILL CREEK 43.0
END DESCRIPTION:
XS GIS Cut Line= 3
      2783755.68     10293253.11      2783660.48     10293144.81
      2783305.66      10292953.1
#Sta/Elev= 30
  4855.8 1436.47  4859.1 1436.47  4862.9 1435.43  4869.6 1436.04  4891.4 1434.38
  4934.1 1430.14  4940.7 1430.62  4975.8 1428.39  4995.6 1424.91  4995.9 1424.41
  4999.4 1424.41  4999.6 1424.91  5012.6 1425.37  5040.2 1430.04  5050.7 1430.26
  5056.4 1431.69  5072.6 1431.44  5094.5 1433.76  5100.1 1433.18  5107.7 1434.42
  5130.5 1436.18  5175.9 1438.53  5203.9 1440.88    5210 1441.97  5247.7 1444.66
  5263.9 1447.12  5269.5 1447.09    5301  1451.8  5367.6 1457.56  5403.3 1459.44
#Mann= 3 ,-1 , 0
  4855.8     .05       0  4995.6     .05       0  4999.6     .05       0
Bank Sta=4995.6,4999.6
XS Rating Curve= 0 ,0
Exp/Cntr=0.3,0.1

Type RM Length L Ch R = 1 ,21000   ,500,500,500
BEGIN DESCRIPTION:
MAGILL CREEK 42.0
END DESCRIPTION:
XS GIS Cut Line= 3
      2783805.69     10293553.09      2784075.51      10292926.3
      2783555.69     10292553.12
#Sta/Elev= 30
  4317.6 1449.18  4408.1 1447.61  4513.5  1443.9  4589.8 1444.19  4796.6 1430.67
  4840.8 1425.39    4949 1422.84  4970.8 1420.49  4981.7  1420.5  4990.9 1417.19
  4991.2 1416.69  4994.9 1417.19    4999 1418.88    5010 1417.75  5016.1  1420.5
  5030.9  1419.1    5037 1423.06  5045.6 1423.47  5051.8 1426.33  5060.3 1426.17
  5066.5 1427.49  5095.9 1426.32  5152.4 1428.92  5167.2 1428.02  5253.1 1429.47
  5332.2 1431.92    5440 1437.04  5517.1 1441.19  5541.1 1441.27  5639.9  1445.9
#Mann= 5 ,-1 , 0
  4317.6     .05       0  4990.9     .05       0  4994.9     .05       0
    5440     .12       0  5541.1     .05       0
Bank Sta=4990.9,4994.9
XS Rating Curve= 0 ,0
Exp/Cntr=0.3,0.1

Type RM Length L Ch R = 1 ,20500   ,500,500,500
BEGIN DESCRIPTION:
MAGILL CREEK 41.0
END DESCRIPTION:
XS GIS Cut Line= 3
      2784405.69     10293403.07      2784472.22     10292982.81
      2784555.69     10292653.11
#Sta/Elev= 30
  4574.5 1432.37  4655.5 1427.35  4716.2 1425.42  4868.1    1418  4878.2 1418.33
    4925 1414.89  4959.2 1413.85  4985.3 1411.04  4985.6 1410.54  4989.3 1411.04
    5010 1413.04  5020.3 1412.23    5030 1412.93  5035.1 1415.12    5071 1414.24
  5092.5 1414.88  5102.8 1416.14  5133.8 1415.55  5144.1 1416.25  5158.1 1414.83
  5185.4 1416.84  5199.2 1415.91  5226.6 1416.75    5235 1417.95  5240.2 1417.46
  5267.9 1420.57  5281.2 1418.42  5292.3 1419.29  5322.2 1417.27  5340.1 1417.99
#Mann= 4 ,-1 , 0
  4574.5     .05       0  4985.3     .05       0  4989.3     .05       0
  5292.3     .12       0
Bank Sta=4985.3,4989.3
XS Rating Curve= 0 ,0
Exp/Cntr=0.3,0.1

Type RM Length L Ch R = 1 ,20000   ,500,500,500
BEGIN DESCRIPTION:
MAGILL CREEK 40.0
END DESCRIPTION:
XS GIS Cut Line= 3
      2784755.68     10293703.11      2784861.85     10292760.47
      2784355.68     10292553.11
#Sta/Elev= 30
  4051.4 1443.41  4061.5  1440.7  4091.3 1438.14  4096.4 1439.46  4202.3 1435.74
  4242.6 1428.16  4276.3 1428.39  4292.9  1432.2    4303 1432.23    4313 1427.95
  4333.2 1424.59  4361.2 1424.49  4366.3 1427.47  4383.5 1425.43  4413.7 1427.44
  4451.2 1424.58  4546.2 1423.53  4923.5 1410.19  4983.9    1405  4984.2  1404.5
  4987.9    1405  4990.9 1407.35  5003.7 1405.32  5012.1 1406.35  5049.9 1406.87
  5169.3 1414.79  5228.2 1415.66  5363.3  1418.6  5430.3 1422.99    5547 1426.17
#Mann= 7 ,-1 , 0
  4051.4     .05       0  4923.5     .12       0  4983.9     .07       0
  4987.9     .12       0  5012.1     .05       0  5228.2     .12       0
  5430.3     .05       0
Bank Sta=4983.9,4987.9
XS Rating Curve= 0 ,0
Exp/Cntr=0.3,0.1

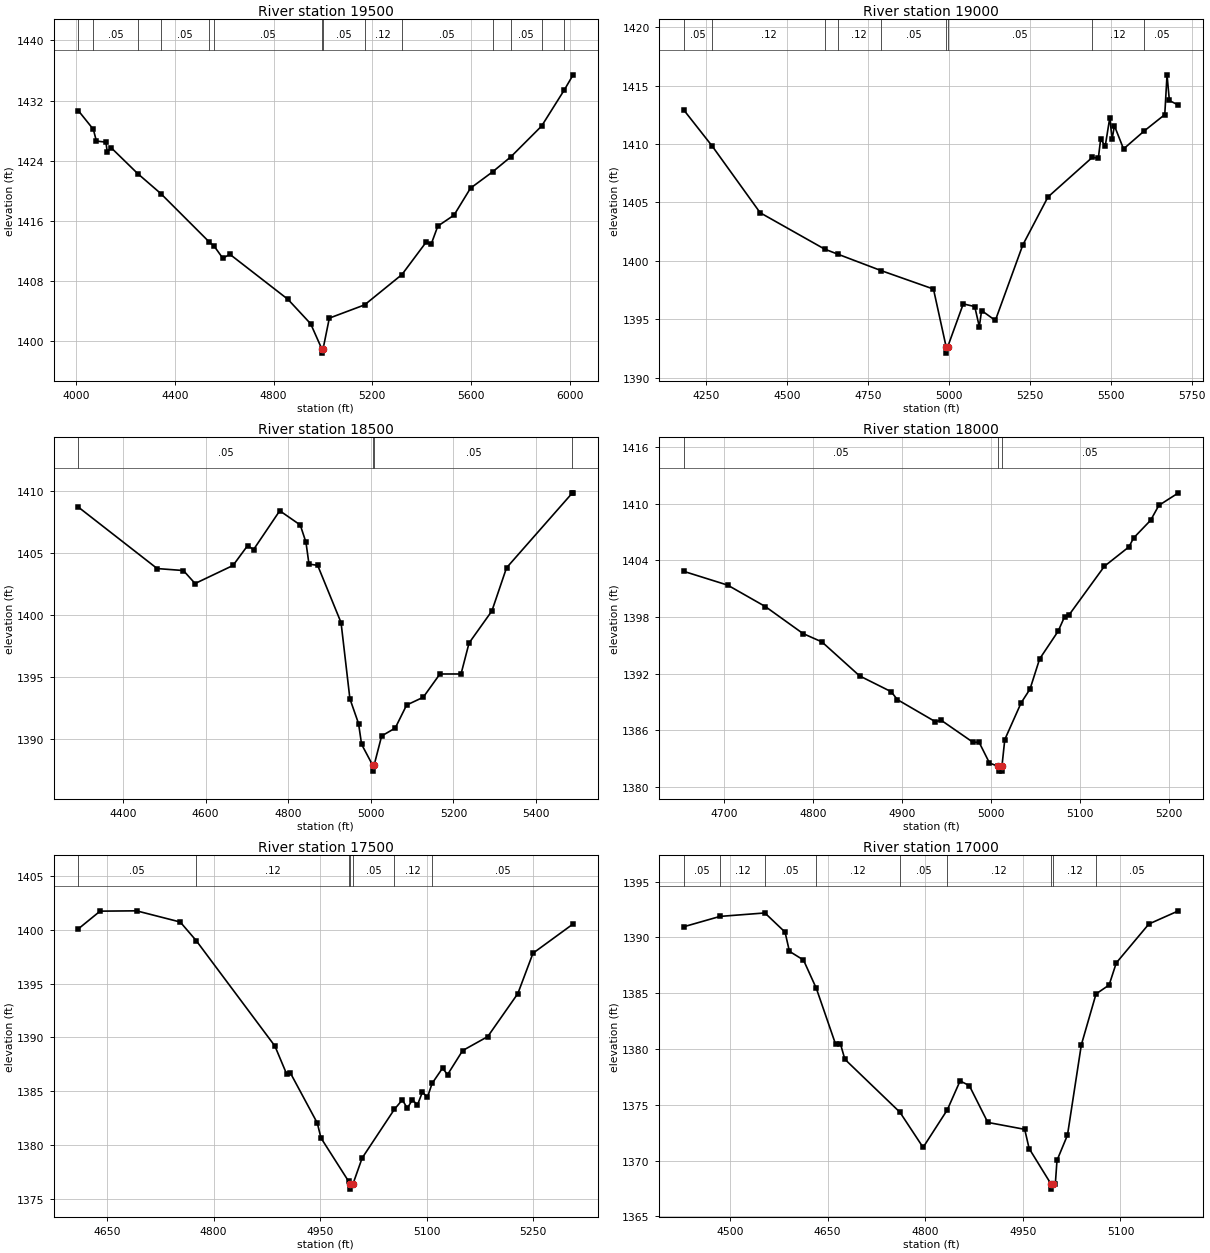
Type RM Length L Ch R = 1 ,19500   ,500,500,500
BEGIN DESCRIPTION:
MAGILL CREEK 39.0
END DESCRIPTION:
XS GIS Cut Line= 3
      2785405.69     10293503.15      2785193.01     10292534.73
      2784205.71     10292303.12
#Sta/Elev= 30
  4008.5 1430.67  4069.6 1428.17  4081.9 1426.61  4120.6 1426.47  4125.7 1425.17
  4141.6 1425.73    4249 1422.29    4343 1419.62  4540.1 1413.15  4558.6 1412.65
  4594.3 1411.01  4622.8 1411.54  4858.3 1405.54  4950.5 1402.28  4996.3 1398.88
  4996.5 1398.38  5000.3 1398.88    5026 1403.04  5168.8  1404.8  5320.3 1408.84
  5418.1 1413.14  5438.9 1412.89  5465.7 1415.29  5531.4 1416.75  5598.2 1420.34
    5688 1422.52  5761.9 1424.52  5886.4 1428.61  5978.8 1433.44  6014.1 1435.43
#Mann= 14 ,-1 , 0
  4008.5     .12       0  4069.6     .05       0    4249     .12       0
    4343     .05       0  4540.1     .12       0  4558.6     .05       0
  4996.3     .05       0  5000.3     .05       0  5168.8     .12       0
  5320.3     .05       0    5688     .12       0  5761.9     .05       0
  5886.4     .12       0  5978.8     .05       0
Bank Sta=4996.3,5000.3
XS Rating Curve= 0 ,0
Exp/Cntr=0.3,0.1

Type RM Length L Ch R = 1 ,19000   ,500,500,500
BEGIN DESCRIPTION:
MAGILL CREEK 38.0
END DESCRIPTION:
XS GIS Cut Line= 3
      2786005.65     10292553.08      2785351.02     10292060.91
      2784855.67      10291553.1
#Sta/Elev= 30
    4181 1412.94    4270  1409.8  4417.3 1404.12  4616.7    1401  4657.2 1400.57
  4790.1 1399.17  4952.6 1397.58    4992 1392.59  4992.3 1392.09    4996 1392.59
  5044.6 1396.31  5080.1 1396.08  5094.2 1394.35  5101.2 1395.74  5143.7 1394.89
  5228.5 1401.36  5306.2 1405.47  5443.3 1408.87  5461.8 1408.79    5469 1410.44
  5483.1 1409.83  5497.3 1412.28  5504.3  1410.4  5511.4 1411.58  5539.7 1409.59
    5604 1411.14    5667 1412.53    5674 1415.94  5681.2 1413.74  5709.4 1413.34
#Mann= 9 ,-1 , 0
    4181     .05       0    4270     .12       0  4616.7     .05       0
  4657.2     .12       0  4790.1     .05       0    4992     .05       0
    4996     .05       0  5443.3     .12       0    5604     .05       0
Bank Sta=4992,4996
XS Rating Curve= 0 ,0
Exp/Cntr=0.3,0.1

Type RM Length L Ch R = 1 ,18500   ,500,500,500
BEGIN DESCRIPTION:
MAGILL CREEK 37.0
END DESCRIPTION:
XS GIS Cut Line= 3
      2786105.67      10292203.1      2785591.69     10291715.31
      2785105.66     10291653.11
#Sta/Elev= 30
  4291.4 1408.71  4482.5 1403.74    4546 1403.58  4574.3 1402.53  4666.2 1403.99
  4701.7  1405.6  4715.9 1405.27  4779.4 1408.41  4829.1 1407.26  4842.9 1405.86
  4850.2  1404.1  4871.2    1404  4927.9 1399.37  4949.3 1393.22  4970.3 1391.21
  4977.6 1389.54  5004.1 1387.87  5004.3 1387.37  5008.1 1387.87  5026.2 1390.21
  5059.1 1390.85  5086.7 1392.71    5127 1393.34  5167.4 1395.22  5218.5 1395.22
  5237.9 1397.72  5293.2 1400.31  5328.7  1403.8  5488.4 1409.86    5490 1409.86
#Mann= 4 ,-1 , 0
  4291.4     .05       0  5004.1     .05       0  5008.1     .05       0
  5488.4     .12       0
Bank Sta=5004.1,5008.1
XS Rating Curve= 0 ,0
Exp/Cntr=0.3,0.1

Type RM Length L Ch R = 1 ,18000   ,500,500,500
BEGIN DESCRIPTION:
MAGILL CREEK 36.0
END DESCRIPTION:
XS GIS Cut Line= 3
      2785905.66     10291503.09      2785658.36     10291261.68
      2785455.65      10291203.1
#Sta/Elev= 30
  4654.4 1402.82  4703.9 1401.36  4746.3 1399.09  4788.7 1396.23  4809.9 1395.35
  4852.3 1391.75  4887.8 1390.08  4894.8 1389.24  4937.2 1386.92  4944.3 1387.04
  4979.6 1384.74  4986.8 1384.71  4998.4 1382.53  5008.4 1382.17  5008.7 1381.67
  5012.2 1381.67  5012.4 1382.17  5015.6 1385.01    5034  1388.9    5044 1390.36
  5054.8 1393.55  5075.6 1396.48  5082.9 1398.02  5088.1 1398.23  5127.7 1403.36
  5155.3 1405.41  5160.5 1406.35  5179.7 1408.23  5188.9  1409.8    5211 1411.13
#Mann= 3 ,-1 , 0
  4654.4     .05       0  5008.4     .05       0  5012.4     .05       0
Bank Sta=5008.4,5012.4
XS Rating Curve= 0 ,0
Exp/Cntr=0.3,0.1

Type RM Length L Ch R = 1 ,17500   ,500,500,500
BEGIN DESCRIPTION:
MAGILL CREEK 35.0
END DESCRIPTION:
XS GIS Cut Line= 3
      2786105.68     10291303.07      2786019.52      10290922.3
      2785805.69     10290703.12
#Sta/Elev= 30
  4609.6 1400.08  4640.3 1401.73  4691.6 1401.76  4753.1 1400.72  4775.5    1399
  4886.4 1389.19  4902.9 1386.59    4908 1386.71  4946.1 1382.03  4951.2 1380.65
  4990.3  1376.6  4992.4 1376.39  4992.6 1375.89  4996.4 1376.39  5009.2 1378.78
  5054.5  1383.3  5065.8 1384.19  5072.8  1383.4    5080 1384.21    5087  1383.7
  5094.1 1384.92  5101.1 1384.41  5107.6 1385.71  5122.4 1387.14  5129.4 1386.53
  5150.7 1388.77    5186 1390.07  5228.4 1394.07  5249.7 1397.82  5306.2 1400.54
#Mann= 7 ,-1 , 0
  4609.6     .05       0  4775.5     .12       0  4990.3     .05       0
  4992.4     .05       0  4996.4     .05       0  5054.5     .12       0
  5107.6     .05       0
Bank Sta=4992.4,4996.4
XS Rating Curve= 0 ,0
Exp/Cntr=0.3,0.1

Type RM Length L Ch R = 1 ,17000   ,500,500,500
BEGIN DESCRIPTION:
MAGILL CREEK 34.0
END DESCRIPTION:
XS GIS Cut Line= 3
      2786755.69     10291003.12      2786371.56      10290580.5
      2786305.69     10290403.14
#Sta/Elev= 30
  4428.9 1390.96  4484.8 1391.89  4553.7  1392.2  4584.7 1390.48  4591.4 1388.76
    4613 1387.98  4632.8 1385.43  4662.4 1380.42  4669.8 1380.46  4676.6 1379.08
  4761.1 1374.34  4796.8 1371.18    4834 1374.55  4853.6 1377.14  4867.8 1376.72
  4896.2 1373.42  4952.9  1372.8  4959.7 1371.08  4992.9 1367.94  4993.1 1367.44
  4996.9 1367.94    5000 1367.94  5002.5 1370.01  5018.6 1372.28  5039.9 1380.37
  5062.5 1384.94  5082.6 1385.74  5093.6 1387.72  5143.7 1391.21  5189.2 1392.39
#Mann= 9 ,-1 , 0
  4428.9     .05       0  4484.8     .12       0  4553.7     .05       0
  4632.8     .12       0  4761.1     .05       0    4834     .12       0
  4992.9     .07       0  4996.9     .12       0  5062.5     .05       0
Bank Sta=4992.9,4996.9
XS Rating Curve= 0 ,0
Exp/Cntr=0.3,0.1

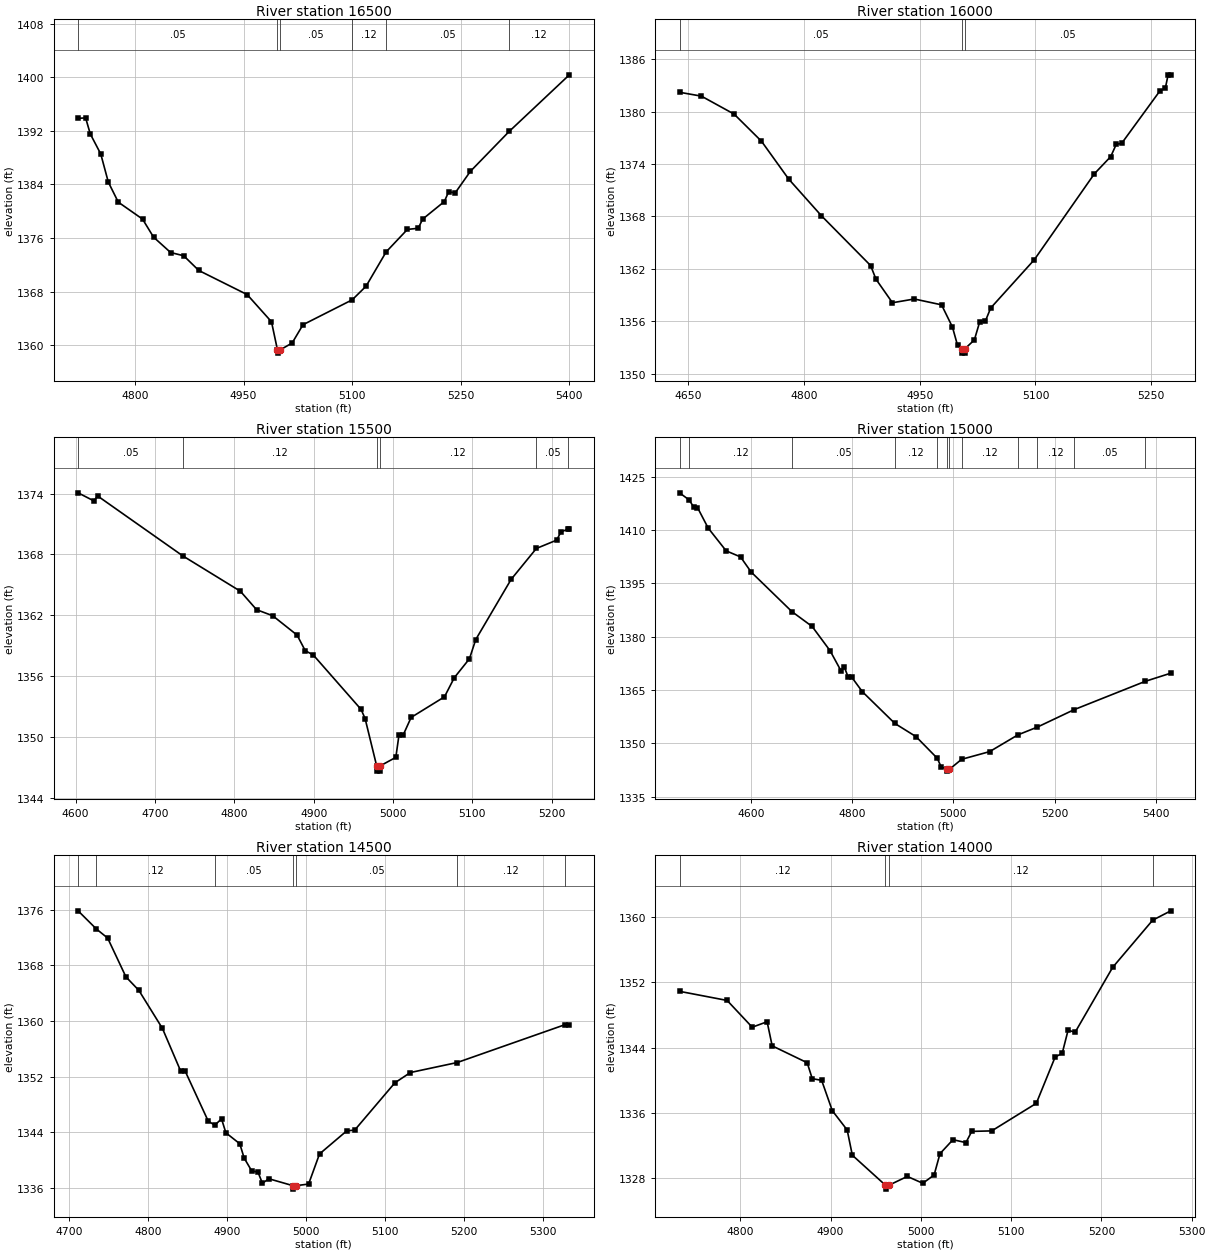
Type RM Length L Ch R = 1 ,16500   ,500,500,500
BEGIN DESCRIPTION:
MAGILL CREEK 33.0
END DESCRIPTION:
XS GIS Cut Line= 3
       2787105.7     10290503.12      2786838.29     10290425.32
      2786505.69     10290203.11
#Sta/Elev= 30
  4721.5 1393.87  4731.9 1393.93  4738.3 1391.54  4752.8 1388.54  4763.2 1384.35
    4777 1381.35  4810.5 1378.82  4825.7 1376.13  4849.3 1373.83  4867.3 1373.35
  4888.2 1371.15    4955 1367.55  4988.6 1363.49  4996.8 1359.31    4997 1358.81
  5000.8 1359.31  5017.1 1360.32  5032.1 1363.05  5100.1 1366.77  5119.2  1368.8
    5147 1373.93  5176.3 1377.28  5191.3 1377.45  5197.3 1378.81  5227.3 1381.44
  5233.3  1382.9  5242.3 1382.73  5263.3 1385.95  5316.8  1391.9    5400 1400.36
#Mann= 6 ,-1 , 0
  4721.5     .05       0  4996.8     .05       0  5000.8     .05       0
  5100.1     .12       0    5147     .05       0  5316.8     .12       0
Bank Sta=4996.8,5000.8
XS Rating Curve= 0 ,0
Exp/Cntr=0.3,0.1

Type RM Length L Ch R = 1 ,16000   ,500,500,500
BEGIN DESCRIPTION:
MAGILL CREEK 32.0
END DESCRIPTION:
XS GIS Cut Line= 3
      2787305.69     10290253.11      2787051.45     10289996.68
      2786855.69     10289803.12
#Sta/Elev= 30
  4638.9 1382.22  4667.2 1381.78  4709.6 1379.72    4745 1376.62  4780.3 1372.28
  4822.7 1368.08  4886.4 1362.38  4893.4 1360.81  4914.7 1358.12    4943 1358.55
  4978.3 1357.88  4992.4 1355.34    4999 1353.25  5004.6 1352.85  5004.9 1352.35
  5008.4 1352.35  5008.6 1352.85  5020.8 1353.86  5027.8 1355.95  5034.9 1355.98
    5042 1357.52  5098.5 1363.05  5176.3 1372.89  5197.5 1374.86  5204.6 1376.26
  5211.7 1376.38  5261.2 1382.38  5268.2 1382.69  5271.8 1384.22  5275.3 1384.22
#Mann= 3 ,-1 , 0
  4638.9     .05       0  5004.6     .05       0  5008.6     .05       0
Bank Sta=5004.6,5008.6
XS Rating Curve= 0 ,0
Exp/Cntr=0.3,0.1

Type RM Length L Ch R = 1 ,15500   ,500,500,500
BEGIN DESCRIPTION:
MAGILL CREEK 31.0
END DESCRIPTION:
XS GIS Cut Line= 3
      2787555.68     10290203.09       2787473.1     10289814.87
      2787405.69     10289603.14
#Sta/Elev= 30
  4603.1 1374.08  4622.8 1373.29  4627.9 1373.76  4734.8 1367.87  4807.6 1364.37
    4828 1362.55  4848.4 1361.95  4879.1 1360.04  4889.3 1358.51  4899.6 1358.07
  4959.7 1352.71  4964.8  1351.8  4979.4 1347.12  4979.6 1346.62  4983.1 1346.62
  4983.4 1347.12  5003.5 1347.98  5007.5 1350.19  5012.8 1350.19  5022.8 1351.92
  5064.8 1353.95  5077.2 1355.84  5096.3 1357.71  5104.2  1359.6  5148.8 1365.54
  5180.6 1368.59  5206.1 1369.41  5211.7 1370.23    5221 1370.51  5222.2 1370.51
#Mann= 6 ,-1 , 0
  4603.1     .05       0  4734.8     .12       0  4979.4     .07       0
  4983.4     .12       0  5180.6     .05       0    5221     .12       0
Bank Sta=4979.4,4983.4
XS Rating Curve= 0 ,0
Exp/Cntr=0.3,0.1

Type RM Length L Ch R = 1 ,15000   ,500,500,500
BEGIN DESCRIPTION:
MAGILL CREEK 30.0
END DESCRIPTION:
XS GIS Cut Line= 3
      2788305.71     10290003.13      2787927.69     10289616.81
       2787555.7     10289403.12
#Sta/Elev= 30
  4459.5 1420.42  4478.6  1418.4  4487.7 1416.34  4494.9 1416.28    4516 1410.51
  4551.5  1404.1  4579.8  1402.4  4600.9 1398.13  4681.1 1387.03  4721.2 1382.83
  4756.5 1376.03  4777.8 1370.45  4784.8 1371.36  4791.9 1368.74  4798.9 1368.64
  4820.2  1364.5  4884.4 1355.56  4926.2 1351.85  4968.1 1345.77  4975.8 1343.32
  4987.9 1342.65  4988.2 1342.15    4992 1342.65  5016.1 1345.47  5071.5 1347.64
  5127.3 1352.35  5165.7 1354.54  5238.4 1359.45  5378.9 1367.42    5429  1369.7
#Mann= 12 ,-1 , 0
  4459.5     .05       0  4478.6     .12       0  4681.1     .05       0
  4884.4     .12       0  4968.1     .05       0  4987.9     .05       0
    4992     .05       0  5016.1     .12       0  5127.3     .05       0
  5165.7     .12       0  5238.4     .05       0  5378.9     .12       0
Bank Sta=4987.9,4992
XS Rating Curve= 0 ,0
Exp/Cntr=0.3,0.1

Type RM Length L Ch R = 1 ,14500   ,500,500,500
BEGIN DESCRIPTION:
MAGILL CREEK 29.0
END DESCRIPTION:
XS GIS Cut Line= 3
      2788305.69     10289503.12      2788186.54     10289240.05
      2787855.69     10289203.11
#Sta/Elev= 30
  4711.2 1375.86  4734.3 1373.25  4748.6 1371.94  4771.7 1366.36  4788.1 1364.41
  4817.9 1358.94    4841  1352.8  4846.5 1352.84  4875.9 1345.59  4884.2 1345.02
  4892.7 1345.92  4898.2 1343.92  4915.8 1342.34  4921.3 1340.29  4930.8 1338.45
  4938.9 1338.25  4944.4 1336.66  4952.7  1337.3    4983 1336.31  4983.3 1335.81
  4987.2 1336.31  5002.9 1336.54  5016.7 1340.87  5051.2  1344.2  5061.2  1344.3
  5112.1 1351.11  5131.7 1352.59    5191 1354.03  5327.2 1359.47  5332.9  1359.5
#Mann= 7 ,-1 , 0
  4711.2     .05       0  4734.3     .12       0  4884.2     .05       0
    4983     .05       0  4987.2     .05       0    5191     .12       0
  5327.2     .05       0
Bank Sta=4983,4987.2
XS Rating Curve= 0 ,0
Exp/Cntr=0.3,0.1

Type RM Length L Ch R = 1 ,14000   ,500,500,500
BEGIN DESCRIPTION:
MAGILL CREEK 28.0
END DESCRIPTION:
XS GIS Cut Line= 3
       2788455.7     10289003.14      2788333.48     10288765.41
       2788155.7     10288553.13
#Sta/Elev= 30
  4732.7 1350.91  4785.4 1349.79  4813.2  1346.5  4829.7 1347.17  4835.3 1344.21
  4874.1 1342.13  4879.7 1340.17  4890.1 1339.97  4901.9 1336.24  4918.4 1333.86
  4924.1 1330.76  4960.6 1327.09  4960.9 1326.59    4965 1327.09    4985 1328.15
  5002.2 1327.31  5014.7 1328.33  5021.2 1330.95  5035.6 1332.67  5049.9 1332.31
  5056.4 1333.69  5078.5 1333.75  5127.9 1337.14  5148.8 1342.84  5156.6 1343.29
  5163.1 1346.13  5170.9 1345.88  5212.5 1353.86  5256.8 1359.66  5276.9 1360.81
#Mann= 4 ,-1 , 0
  4732.7     .12       0  4960.6     .07       0    4965     .12       0
  5256.8     .05       0
Bank Sta=4960.6,4965
XS Rating Curve= 0 ,0
Exp/Cntr=0.3,0.1

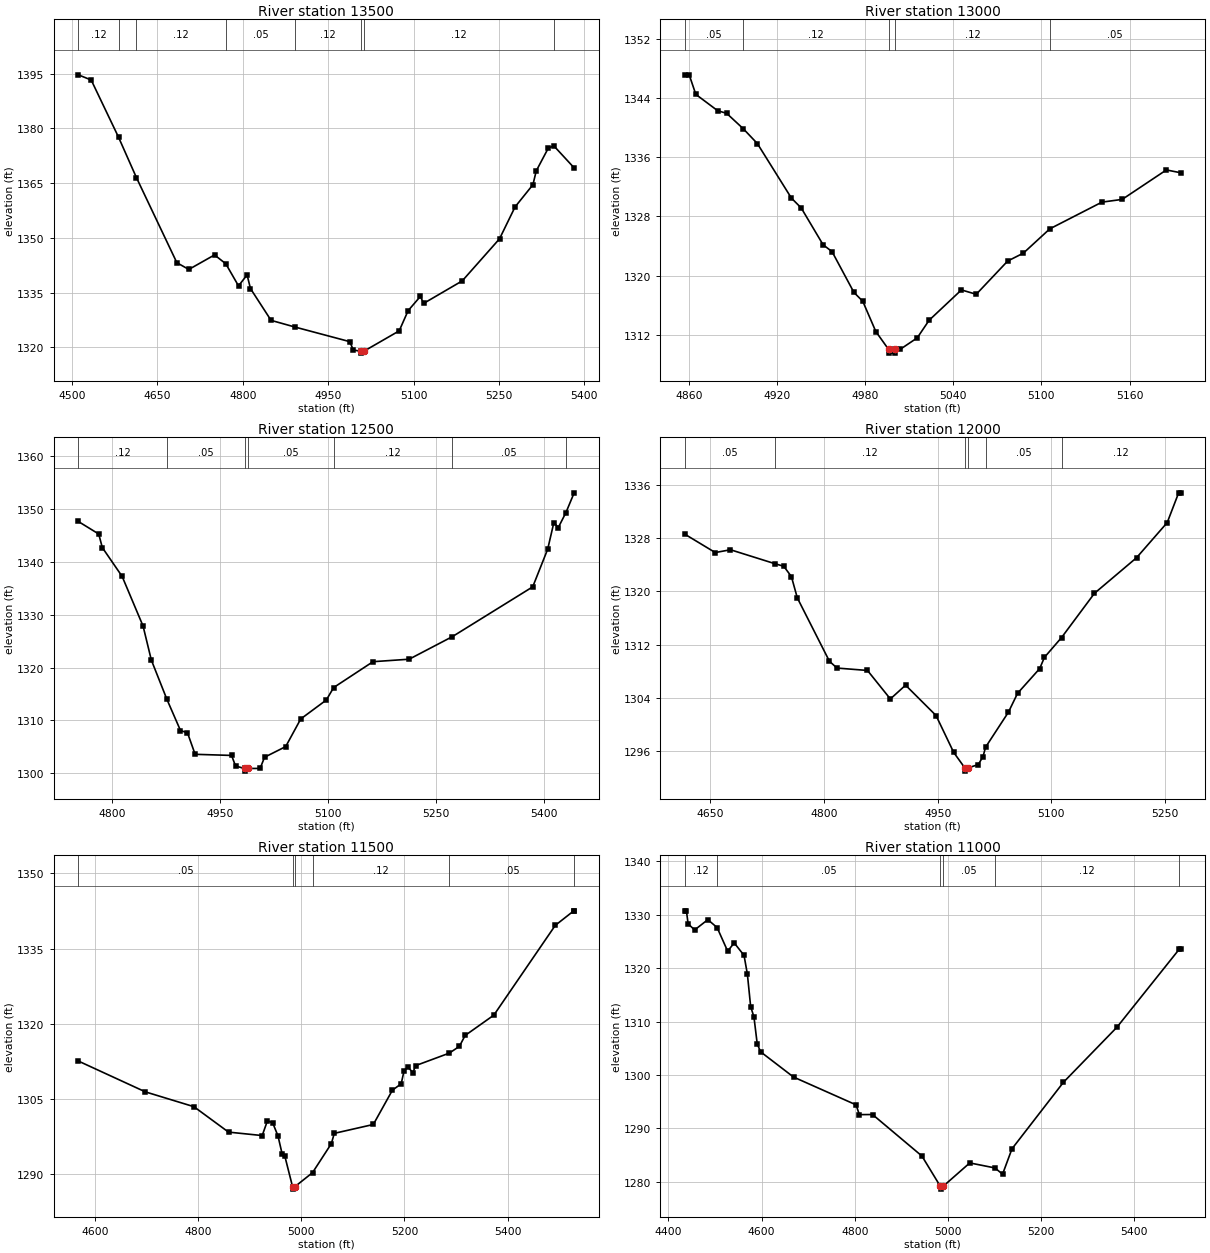
Type RM Length L Ch R = 1 ,13500   ,500,500,500
BEGIN DESCRIPTION:
MAGILL CREEK 27.0
END DESCRIPTION:
XS GIS Cut Line= 3
       2789055.7     10288903.12       2788647.8     10288633.42
      2788455.69     10288303.12
#Sta/Elev= 30
    4511 1394.67  4533.6 1393.25  4581.6 1377.59    4613 1366.53  4684.1 1343.19
  4705.1 1341.34  4750.3 1345.32  4770.1 1342.89  4792.4 1336.84  4807.5 1339.84
  4813.4 1336.11  4849.6 1327.39  4891.8 1325.55    4988 1321.55    4994 1319.26
  5007.9 1318.91  5008.2 1318.41  5012.4 1318.91  5074.7 1324.51  5090.4 1330.05
  5111.9 1333.94  5117.7 1332.04  5185.5 1338.21    5251 1349.74  5278.3 1358.48
  5309.7 1364.57  5315.5 1368.35    5337 1374.69  5346.8 1375.14  5382.1 1369.17
#Mann= 8 ,-1 , 0
    4511     .12       0  4581.6     .05       0    4613     .12       0
  4770.1     .05       0  4891.8     .12       0  5007.9     .07       0
  5012.4     .12       0  5346.8     .05       0
Bank Sta=5007.9,5012.4
XS Rating Curve= 0 ,0
Exp/Cntr=0.3,0.1

Type RM Length L Ch R = 1 ,13000   ,500,500,500
BEGIN DESCRIPTION:
MAGILL CREEK 26.0
END DESCRIPTION:
XS GIS Cut Line= 3
      2789155.69     10288503.12      2789037.62     10288422.62
      2788855.65      10288353.1
#Sta/Elev= 30
  4857.1 1347.14  4860.1 1347.14  4864.6  1344.5  4879.5 1342.29  4885.6 1341.94
  4896.9 1339.86  4906.5 1337.86  4929.7 1330.49  4936.4 1329.15  4951.3 1324.18
  4957.4 1323.25  4972.3 1317.74  4978.3 1316.55  4987.2 1312.46  4995.9 1310.04
  4996.2 1309.54  5000.1 1309.54  5000.4 1310.04  5003.7 1310.04  5015.4  1311.6
  5023.5 1313.98  5045.5 1318.08  5055.6 1317.49    5077 1321.98  5087.7 1323.05
  5105.7 1326.33  5141.2 1329.94    5155 1330.31  5185.1 1334.29  5194.8 1333.91
#Mann= 5 ,-1 , 0
  4857.1     .05       0  4896.9     .12       0  4995.9     .07       0
  5000.4     .12       0  5105.7     .05       0
Bank Sta=4995.9,5000.4
XS Rating Curve= 0 ,0
Exp/Cntr=0.3,0.1

Type RM Length L Ch R = 1 ,12500   ,500,500,500
BEGIN DESCRIPTION:
MAGILL CREEK 25.0
END DESCRIPTION:
XS GIS Cut Line= 3
      2789255.66     10287953.12      2789012.14     10287992.59
      2788655.69     10288253.11
#Sta/Elev= 30
  4753.3 1347.64  4781.6 1345.27  4786.6  1342.7  4814.1 1337.25  4843.2 1327.84
  4854.6 1321.44  4876.2 1314.01  4895.1  1308.1  4904.8 1307.67  4915.4  1303.6
    4966 1303.39  4971.5 1301.39    4984 1300.92  4984.3 1300.42  4988.6 1300.92
  5005.6 1300.93  5011.8 1303.05  5041.1 1305.06    5062 1310.29  5097.5 1313.87
  5107.7 1316.23  5162.3 1321.12  5212.5 1321.59  5272.6 1325.87    5384 1335.28
  5404.8 1342.42  5413.3 1347.43  5419.5  1346.5  5430.1 1349.33  5441.5 1353.06
#Mann= 7 ,-1 , 0
  4753.3     .12       0  4876.2     .05       0    4984     .05       0
  4988.6     .05       0  5107.7     .12       0  5272.6     .05       0
  5430.1     .12       0
Bank Sta=4984,4988.6
XS Rating Curve= 0 ,0
Exp/Cntr=0.3,0.1

Type RM Length L Ch R = 1 ,12000   ,500,500,500
BEGIN DESCRIPTION:
MAGILL CREEK 24.0
END DESCRIPTION:
XS GIS Cut Line= 3
      2789005.64     10287653.12      2788623.83     10287691.14
      2788555.68     10287953.12
#Sta/Elev= 30
  4616.3 1328.61  4656.5 1325.85  4676.6 1326.27  4735.4 1324.17  4746.9 1323.79
    4757 1322.24  4764.8 1319.04  4807.2 1309.52  4817.2  1308.5  4857.4 1308.14
  4887.6 1303.86  4907.7 1305.93  4947.9 1301.37  4971.2 1295.83  4985.8 1293.52
  4986.1 1293.02  4990.4 1293.52  5003.6    1294  5009.9 1295.21  5013.3 1296.62
  5043.4 1301.87  5055.5 1304.71  5084.7 1308.42  5090.9  1310.1  5113.6 1313.09
    5157 1319.73  5212.5 1325.07    5253 1330.35  5268.1 1334.82  5270.7 1334.82
#Mann= 6 ,-1 , 0
  4616.3     .05       0  4735.4     .12       0  4985.8     .07       0
  4990.4     .12       0  5013.3     .05       0  5113.6     .12       0
Bank Sta=4985.8,4990.4
XS Rating Curve= 0 ,0
Exp/Cntr=0.3,0.1

Type RM Length L Ch R = 1 ,11500   ,500,500,500
BEGIN DESCRIPTION:
MAGILL CREEK 23.0
END DESCRIPTION:
XS GIS Cut Line= 3
      2788805.71     10287353.12      2788381.25     10287271.67
      2787905.68     10287503.11
#Sta/Elev= 30
  4567.8  1312.6  4697.8 1306.45  4791.8  1303.5  4858.9 1298.43  4924.2 1297.74
  4934.4  1300.7  4944.6 1300.26  4954.8 1297.67  4962.8  1294.1  4967.9 1293.71
    4983 1287.56  4983.3 1287.06  4987.7 1287.56  5021.8 1290.35  5058.3 1296.14
  5063.9 1298.18  5139.6 1299.95  5176.6 1306.79  5193.6 1308.06  5199.2 1310.67
  5206.4 1311.45  5216.2 1310.28  5221.7 1311.69  5286.7 1314.17  5306.4 1315.52
  5317.6  1317.7  5373.2 1321.75  5492.3 1339.65  5528.2 1342.55  5528.9 1342.55
#Mann= 6 ,-1 , 0
  4567.8     .05       0    4983     .05       0  4987.7     .05       0
  5021.8     .12       0  5286.7     .05       0  5528.2     .12       0
Bank Sta=4983,4987.7
XS Rating Curve= 0 ,0
Exp/Cntr=0.3,0.1

Type RM Length L Ch R = 1 ,11000   ,500,500,500
BEGIN DESCRIPTION:
MAGILL CREEK 22.0
END DESCRIPTION:
XS GIS Cut Line= 3
       2788955.7     10287253.12      2788560.16     10286849.95
      2788505.69     10286353.13
#Sta/Elev= 30
  4435.2  1330.7  4438.7  1330.7  4442.3 1328.26  4456.4 1327.13  4484.7 1329.05
  4504.6 1327.57  4527.2 1323.16  4541.3  1324.7  4562.4 1322.37  4569.6 1318.84
  4576.6  1312.8  4583.7 1310.84  4590.7 1305.82  4597.9 1304.34  4668.6 1299.62
  4802.9 1294.42    4810 1292.59  4838.3 1292.61  4944.3 1284.85  4984.1 1279.16
  4984.5 1278.66  4989.5 1279.16  5047.1 1283.56  5101.2 1282.62  5117.5 1281.45
  5137.7  1286.2  5248.3 1298.65  5363.1 1308.94    5497 1323.54  5499.8 1323.59
#Mann= 6 ,-1 , 0
  4435.2     .12       0  4504.6     .05       0  4984.1     .05       0
  4989.5     .05       0  5101.2     .12       0    5497     .05       0
Bank Sta=4984.1,4989.5
XS Rating Curve= 0 ,0
Exp/Cntr=0.3,0.1