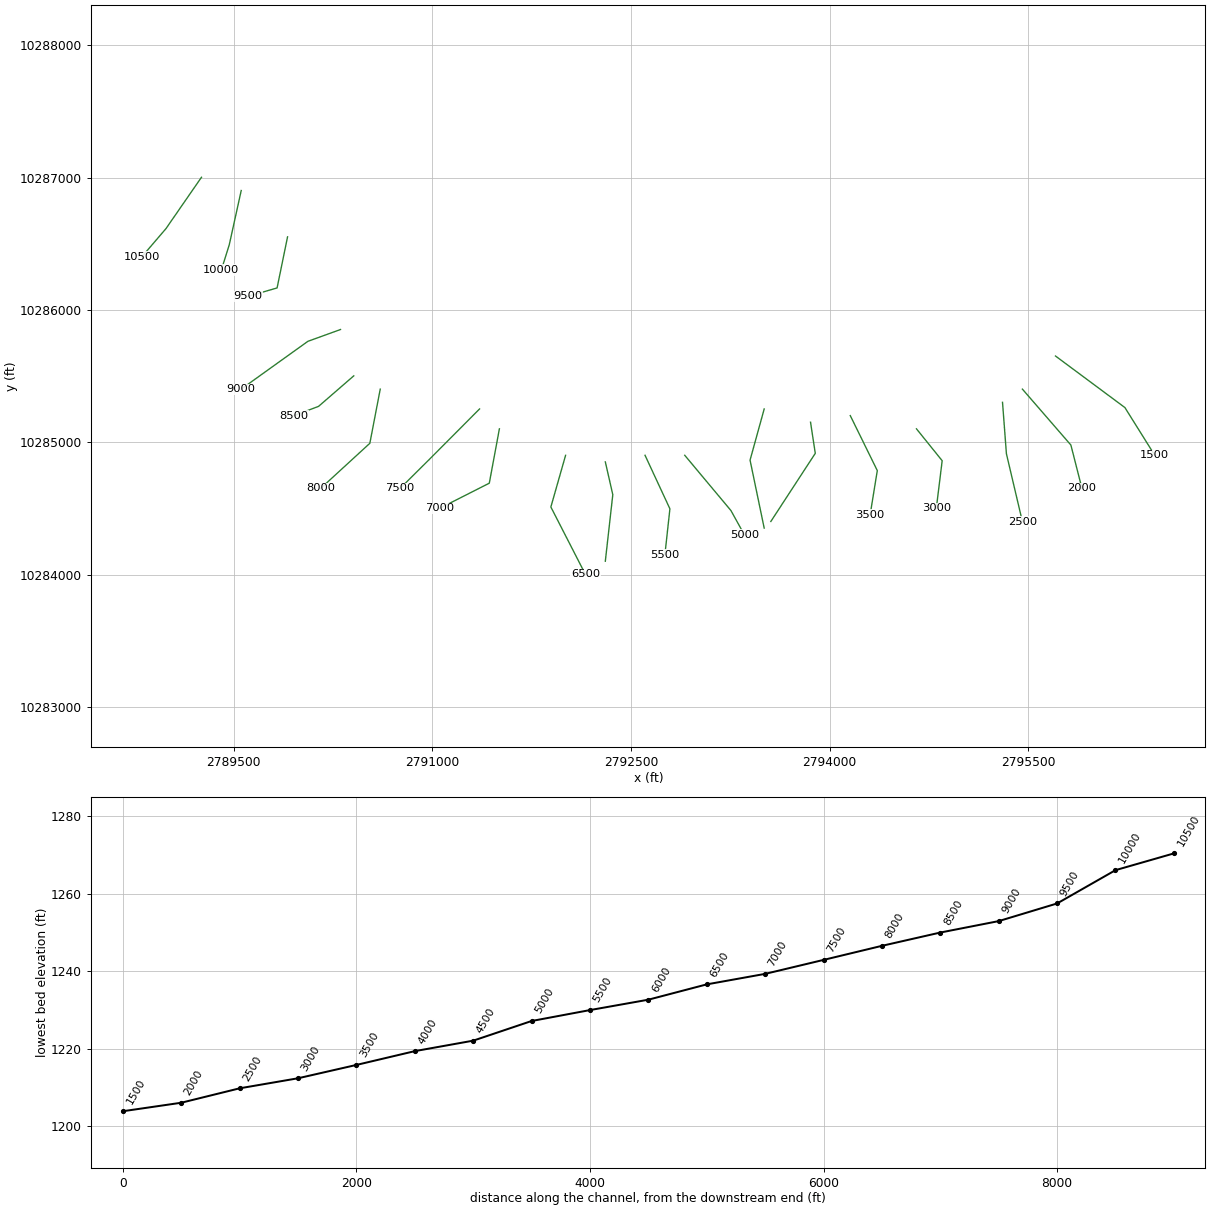
HEC-RAS study MAGILL CREEK.prj: MAGILL CREEK Base Level Engineering

--- MAGILL CREEK.g01 (geometry) --- (continued)

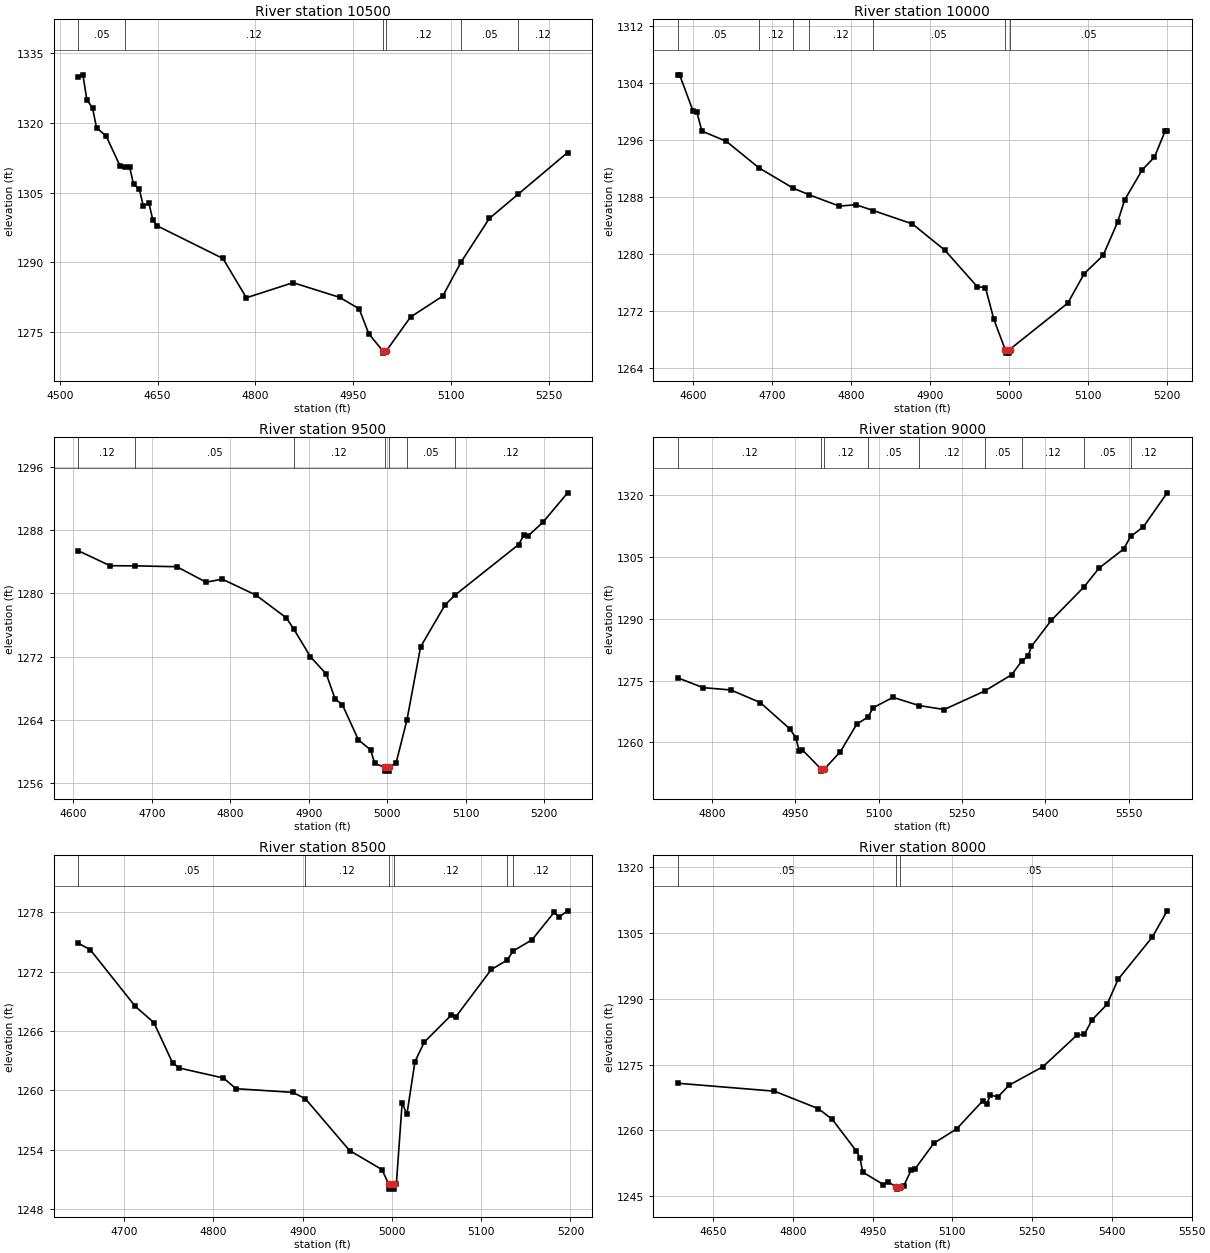
Type RM Length L Ch R = 1 ,10500   ,500,500,500
BEGIN DESCRIPTION:
MAGILL CREEK 21.0
END DESCRIPTION:
XS GIS Cut Line= 3
       2789255.7     10287003.13      2788987.05     10286614.93
      2788805.72     10286403.15
#Sta/Elev= 30
  4527.9    1330  4535.4 1330.39  4541.4 1325.04  4550.2 1323.23  4556.3 1318.99
  4571.2 1317.16  4592.1 1310.84  4600.1  1310.6    4607 1310.55  4613.1 1306.79
  4621.9 1305.77  4627.9 1302.21  4636.7 1302.69  4642.8 1299.03  4649.5 1297.84
  4750.2 1290.82  4786.1 1282.36  4857.7 1285.61  4929.3 1282.44  4959.1 1279.97
  4973.9 1274.59  4995.3 1270.93  4995.8 1270.43  5000.8 1270.93  5037.9 1278.21
  5087.3 1282.72  5115.7 1290.12  5158.7 1299.44  5203.1 1304.69  5278.8 1313.65
#Mann= 6 ,-1 , 0
  4527.9     .05       0  4600.1     .12       0  4995.3     .07       0
  5000.8     .12       0  5115.7     .05       0  5203.1     .12       0
Bank Sta=4995.3,5000.8
XS Rating Curve= 0 ,0
Exp/Cntr=0.3,0.1

Type RM Length L Ch R = 1 ,10000   ,500,500,500
BEGIN DESCRIPTION:
MAGILL CREEK 20.0
END DESCRIPTION:
XS GIS Cut Line= 3
      2789555.68     10286903.08      2789465.52     10286493.79
       2789405.7     10286303.15
#Sta/Elev= 30
  4580.9 1305.13  4583.4 1305.13  4600.2 1300.12  4605.3 1299.88  4611.6 1297.24
  4642.3 1295.82  4683.8 1292.08  4726.8 1289.25  4747.2 1288.31  4785.3 1286.72
  4806.1 1286.92  4828.3  1286.1  4877.8 1284.22  4918.8 1280.53  4959.7 1275.42
    4970 1275.31  4980.7 1270.83    4995 1266.61  4995.4 1266.11  5000.1 1266.11
  5000.5 1266.61  5074.1 1273.12    5095 1277.27  5118.8 1279.81    5137 1284.45
    5146  1287.6  5168.4 1291.83  5183.6 1293.58  5197.2 1297.25  5199.8 1297.25
#Mann= 7 ,-1 , 0
  4580.9     .05       0  4683.8     .12       0  4726.8     .05       0
  4747.2     .12       0  4828.3     .05       0    4995     .05       0
  5000.5     .05       0
Bank Sta=4995,5000.5
XS Rating Curve= 0 ,0
Exp/Cntr=0.3,0.1

Type RM Length L Ch R = 1 ,9500    ,500,500,500
BEGIN DESCRIPTION:
MAGILL CREEK 19.0
END DESCRIPTION:
XS GIS Cut Line= 3
      2789905.69     10286553.13      2789826.51     10286167.06
      2789605.68     10286103.11
#Sta/Elev= 30
  4605.9 1285.42  4646.7 1283.51  4678.8 1283.49  4731.9 1283.38  4769.2 1281.42
  4789.7 1281.81  4832.7 1279.79  4871.3 1276.92  4881.1 1275.46    4902 1272.01
  4922.4 1269.79  4933.6 1266.65  4942.8 1265.93  4963.2 1261.49  4978.9 1260.19
    4984  1258.5  4996.7 1258.02  4997.1 1257.52  5001.8 1257.52  5002.3 1258.02
  5011.3 1258.55  5025.2 1264.03  5042.5 1273.24  5073.7 1278.55  5086.5  1279.8
  5167.4 1286.18  5174.3  1287.4  5179.5 1287.28  5198.7 1289.03  5229.9 1292.73
#Mann= 7 ,-1 , 0
  4605.9     .12       0  4678.8     .05       0  4881.1     .12       0
  4996.7     .07       0  5002.3     .12       0  5025.2     .05       0
  5086.5     .12       0
Bank Sta=4996.7,5002.3
XS Rating Curve= 0 ,0
Exp/Cntr=0.3,0.1

Type RM Length L Ch R = 1 ,9000    ,500,500,500
BEGIN DESCRIPTION:
MAGILL CREEK 18.0
END DESCRIPTION:
XS GIS Cut Line= 3
      2790305.65      10285853.1       2790059.1     10285763.88
      2789555.71     10285403.13
#Sta/Elev= 30
  4737.8 1275.67  4783.7 1273.27  4833.5 1272.71  4886.6 1269.65  4939.8 1263.25
  4950.5 1261.13    4957 1257.75  4962.3 1258.14  4996.2 1253.47  4996.7 1252.97
  5002.1 1253.47    5031 1257.74  5060.5 1264.43  5080.5 1266.11  5089.9 1268.39
  5125.6 1270.91  5172.5 1268.92  5217.7 1267.95  5290.4 1272.43  5339.3 1276.42
  5357.1 1279.66  5368.8    1281  5374.9 1283.31  5410.5 1289.63  5469.8 1297.81
  5496.5 1302.33  5540.7 1306.96  5553.4 1310.03  5576.3 1312.37  5619.3 1320.65
#Mann= 9 ,-1 , 0
  4737.8     .12       0  4996.2     .07       0  5002.1     .12       0
  5080.5     .05       0  5172.5     .12       0  5290.4     .05       0
  5357.1     .12       0  5469.8     .05       0  5553.4     .12       0
Bank Sta=4996.2,5002.1
XS Rating Curve= 0 ,0
Exp/Cntr=0.3,0.1

Type RM Length L Ch R = 1 ,8500    ,500,500,500
BEGIN DESCRIPTION:
MAGILL CREEK 17.0
END DESCRIPTION:
XS GIS Cut Line= 3
      2790405.67      10285503.1      2790139.83     10285272.69
      2789955.73     10285203.13
#Sta/Elev= 30
  4648.2 1274.89  4661.9 1274.22  4712.3  1268.5  4733.2 1266.85  4754.1 1262.79
  4761.7 1262.26  4811.1 1261.25  4825.3 1260.17  4888.9  1259.8    4903 1259.15
  4952.5 1253.92  4988.7    1252  4996.4 1250.52  4996.9 1250.02  5001.9 1250.02
  5002.4 1250.52  5004.9 1250.52  5011.4 1258.75  5016.7 1257.57  5025.8 1262.92
  5036.2 1264.88  5066.4 1267.61  5071.7 1267.46  5111.3 1272.22  5128.9 1273.16
  5135.9  1274.1  5156.9 1275.22  5181.8 1278.01  5187.1 1277.52  5196.8 1278.15
#Mann= 6 ,-1 , 0
  4648.2     .05       0    4903     .12       0  4996.4     .07       0
  5002.4     .12       0  5128.9     .05       0  5135.9     .12       0
Bank Sta=4996.4,5002.4
XS Rating Curve= 0 ,0
Exp/Cntr=0.3,0.1

Type RM Length L Ch R = 1 ,8000    ,500,500,500
BEGIN DESCRIPTION:
MAGILL CREEK 16.0
END DESCRIPTION:
XS GIS Cut Line= 3
      2790605.68     10285403.11      2790527.13     10284993.78
      2790155.69     10284653.12
#Sta/Elev= 30
  4583.2 1270.75  4765.2 1268.94  4847.9 1264.95  4874.2 1262.49  4919.2 1255.29
  4926.2 1253.71  4931.3 1250.47  4970.1 1247.64  4978.2 1248.27  4994.8 1247.09
  4995.3 1246.59  5000.8 1247.09  5008.6 1247.37  5022.7    1251  5029.5 1251.16
  5065.3 1257.09  5107.8 1260.31  5157.2 1266.75  5164.6 1266.04  5171.4 1268.05
  5185.5 1267.62  5206.5 1270.29  5270.6 1274.56  5334.1 1281.72  5348.3 1281.92
  5362.5 1285.19  5390.9 1288.75  5411.8 1294.48    5476  1304.1    5504 1310.09
#Mann= 3 ,-1 , 0
  4583.2     .05       0  4994.8     .05       0  5000.8     .05       0
Bank Sta=4994.8,5000.8
XS Rating Curve= 0 ,0
Exp/Cntr=0.3,0.1

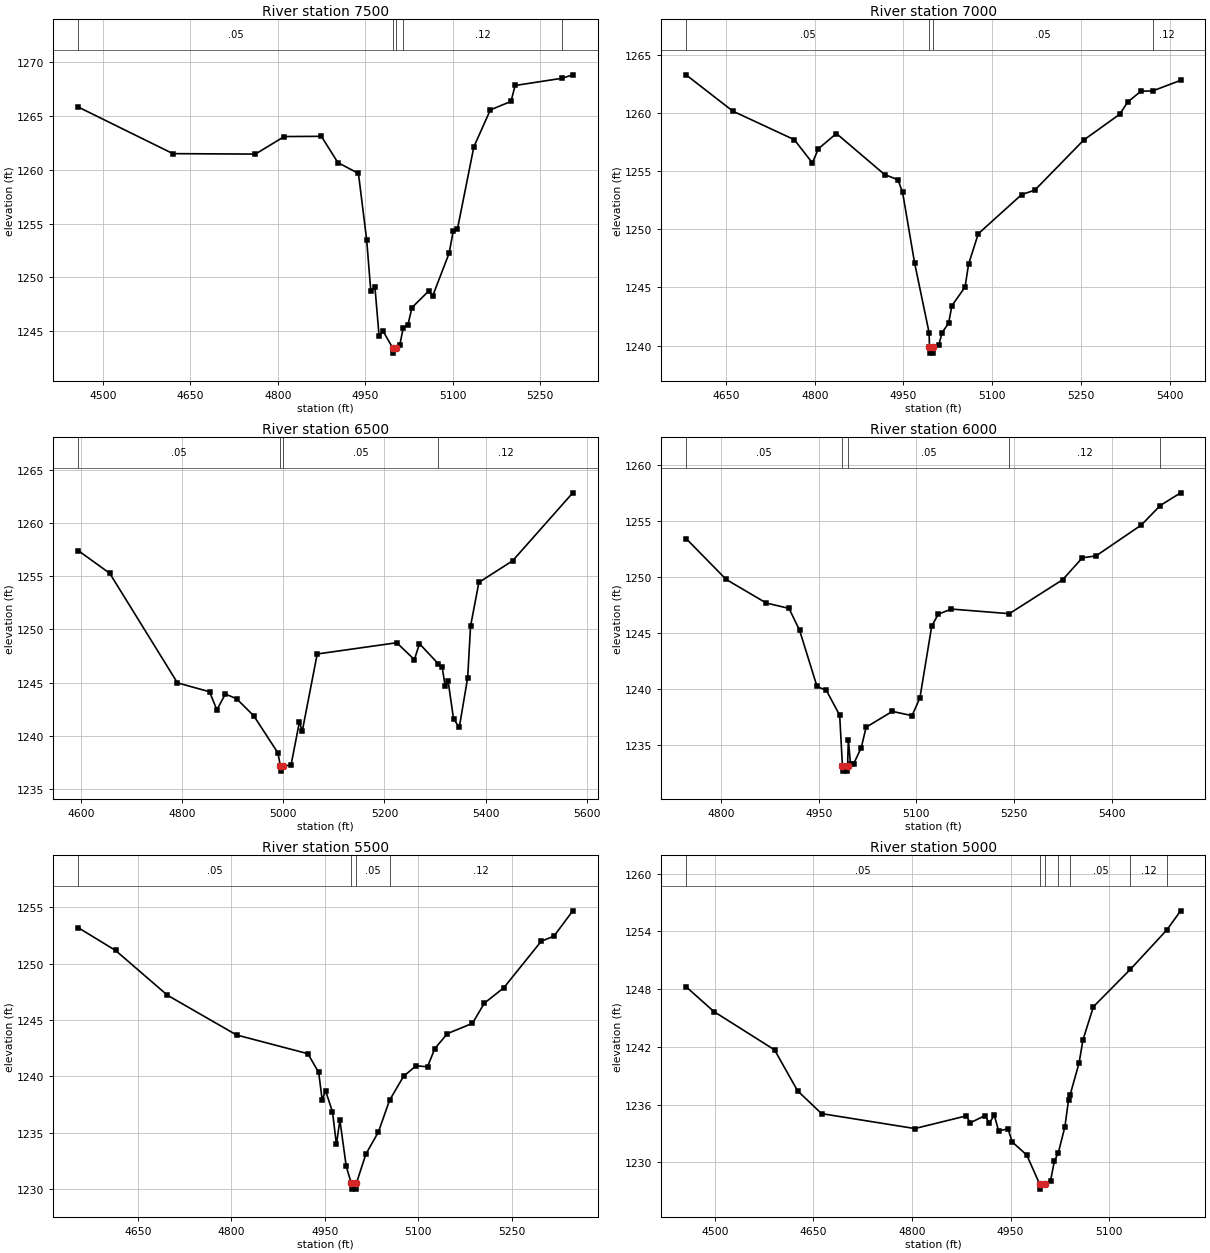
Type RM Length L Ch R = 1 ,7500    ,500,500,500
BEGIN DESCRIPTION:
MAGILL CREEK 15.0
END DESCRIPTION:
XS GIS Cut Line= 3
      2791355.68     10285253.11      2790973.01     10284868.57
       2790755.7     10284653.13
#Sta/Elev= 30
  4457.5 1265.85  4620.1 1261.51  4761.6 1261.47    4811  1263.1  4874.7 1263.12
    4903 1260.68  4938.3 1259.67  4952.5 1253.45  4959.5 1248.71  4966.6 1249.09
  4973.7 1244.56  4980.7 1244.99  4996.9 1243.46  4997.4 1242.96    5003 1243.46
  5009.1 1243.69  5015.1 1245.29  5023.2  1245.6  5030.2  1247.2  5058.5 1248.72
  5065.6 1248.27  5093.9 1252.26    5101 1254.35  5108.1 1254.49  5136.3 1262.15
  5164.6 1265.58    5200 1266.37  5207.1 1267.85  5287.6 1268.52    5306 1268.84
#Mann= 5 ,-1 , 0
  4457.5     .05       0  4996.9     .03       0    5003     .05       0
  5015.1     .12       0  5287.6     .05       0
Bank Sta=4996.9,5003
XS Rating Curve= 0 ,0
Exp/Cntr=0.3,0.1

Type RM Length L Ch R = 1 ,7000    ,500,500,500
BEGIN DESCRIPTION:
MAGILL CREEK 14.0
END DESCRIPTION:
XS GIS Cut Line= 3
      2791505.68     10285103.12      2791429.34     10284692.55
      2791055.71     10284503.13
#Sta/Elev= 30
  4582.4 1263.26  4661.6 1260.14  4765.5 1257.69    4796  1255.7  4806.2 1256.91
  4836.7 1258.22  4918.1  1254.7  4940.7 1254.25  4948.6 1253.17  4968.9 1247.11
  4993.5  1241.1  4994.1 1239.86  4994.6 1239.36  4999.7 1239.36  5000.2 1239.86
  5009.8 1240.05  5015.4 1241.12  5026.4 1241.93    5032 1243.43  5054.3 1245.04
  5060.2    1247  5076.6 1249.61  5149.8 1252.97  5172.3 1253.36  5254.7 1257.65
  5315.9 1259.88  5329.2 1260.92  5351.7 1261.85  5371.7 1261.88  5418.9 1262.79
#Mann= 4 ,-1 , 0
  4582.4     .05       0  4994.1     .03       0  5000.2     .05       0
  5371.7     .12       0
Bank Sta=4994.1,5000.2
XS Rating Curve= 0 ,0
Exp/Cntr=0.3,0.1

Type RM Length L Ch R = 1 ,6500    ,500,500,500
BEGIN DESCRIPTION:
MAGILL CREEK 13.0
END DESCRIPTION:
XS GIS Cut Line= 3
       2792005.7     10284903.16      2791894.31     10284512.73
      2792155.67     10284003.15
#Sta/Elev= 30
    4594 1257.44  4656.4  1255.3  4790.5 1244.97    4854 1244.13  4868.5 1242.42
  4885.2 1243.92  4907.5 1243.47  4941.4 1241.87  4989.2 1238.37  4994.1 1237.15
  4994.6 1236.65  5000.3 1237.15  5015.2 1237.22  5031.8 1241.29  5037.4 1240.41
    5067 1247.69  5224.3 1248.75  5259.3 1247.16  5269.3 1248.66  5306.1 1246.79
  5314.3 1246.43  5320.3 1244.63  5325.9 1245.17  5336.7 1241.59  5348.1 1240.77
  5364.7 1245.46  5370.4 1250.31  5386.9 1254.44  5453.5 1256.47  5572.7 1262.88
#Mann= 4 ,-1 , 0
    4594     .05       0  4994.1     .05       0  5000.3     .05       0
  5306.1     .12       0
Bank Sta=4994.1,5000.3
XS Rating Curve= 0 ,0
Exp/Cntr=0.3,0.1

Type RM Length L Ch R = 1 ,6000    ,500,500,500
BEGIN DESCRIPTION:
MAGILL CREEK 12.0
END DESCRIPTION:
XS GIS Cut Line= 3
      2792305.68     10284853.13      2792362.14      10284605.9
      2792305.69     10284103.16
#Sta/Elev= 30
  4746.4 1253.41    4808 1249.77  4869.5 1247.67  4904.5 1247.19  4920.8 1245.23
  4947.5 1240.24  4961.8 1239.89  4982.3 1237.68  4986.5  1233.2    4987  1232.7
    4994  1232.7  4994.5  1233.2  4995.6  1235.5  4998.9 1233.37  5003.9 1233.37
  5015.5  1234.8  5022.9 1236.61  5063.2 1238.02  5093.4 1237.64  5105.5 1239.22
  5123.6  1245.6  5133.6 1246.67  5153.7 1247.13  5242.8 1246.72  5324.8 1249.75
    5355  1251.7  5375.8 1251.86  5445.6 1254.62  5474.5 1256.35  5505.9 1257.48
#Mann= 5 ,-1 , 0
  4746.4     .05       0  4986.5     .03       0  4994.5     .05       0
  5242.8     .12       0  5474.5     .05       0
Bank Sta=4986.5,4994.5
XS Rating Curve= 0 ,0
Exp/Cntr=0.3,0.1

Type RM Length L Ch R = 1 ,5500    ,500,500,500
BEGIN DESCRIPTION:
MAGILL CREEK 11.0
END DESCRIPTION:
XS GIS Cut Line= 3
      2792605.69     10284903.11      2792793.53     10284498.92
      2792755.68     10284153.09
#Sta/Elev= 30
  4554.3 1253.19  4614.3 1251.17  4697.6  1247.2  4808.4 1243.68  4922.9 1242.02
  4940.2 1240.36  4945.8 1237.94  4951.3 1238.73  4962.3 1236.88  4968.7 1233.98
  4974.2 1236.15  4984.4 1232.04  4992.6 1230.52  4993.1 1230.02  5000.1 1230.02
  5000.6 1230.52  5015.9 1233.12    5036 1235.08  5053.9 1237.89  5076.3 1240.01
  5096.4 1240.95  5114.8 1240.86  5126.6 1242.48  5146.7  1243.8  5186.9 1244.71
    5206  1246.5  5237.2 1247.86  5297.2 1251.98  5317.7 1252.44  5347.9 1254.68
#Mann= 4 ,-1 , 0
  4554.3     .05       0  4992.6     .03       0  5000.6     .05       0
  5053.9     .12       0
Bank Sta=4992.6,5000.6
XS Rating Curve= 0 ,0
Exp/Cntr=0.3,0.1

Type RM Length L Ch R = 1 ,5000    ,500,500,500
BEGIN DESCRIPTION:
MAGILL CREEK 10.0
END DESCRIPTION:
XS GIS Cut Line= 3
      2792905.66     10284903.14      2793254.39     10284485.88
       2793355.7     10284303.08
#Sta/Elev= 30
  4456.2 1248.25  4498.5 1245.67  4590.9 1241.68  4626.1 1237.41  4662.5 1235.05
  4804.4  1233.5  4882.4 1234.81    4889  1234.1  4911.1 1234.85  4917.6 1234.08
  4925.4 1234.87  4931.9 1233.26  4946.2 1233.46  4952.7  1232.1  4974.8 1230.74
  4994.5  1227.7    4995  1227.2  5002.6  1227.7  5010.9 1228.06  5016.7 1230.08
  5022.8    1231  5032.7 1233.65  5038.4  1236.5  5040.9 1237.04  5054.4 1240.33
  5060.3 1242.73  5076.2 1246.17  5132.5 1250.06    5188 1254.16    5209 1256.14
#Mann= 7 ,-1 , 0
  4456.2     .05       0  4994.5     .03       0  5002.6     .05       0
  5022.8     .12       0  5040.9     .05       0  5132.5     .12       0
    5188     .05       0
Bank Sta=4994.5,5002.6
XS Rating Curve= 0 ,0
Exp/Cntr=0.3,0.1

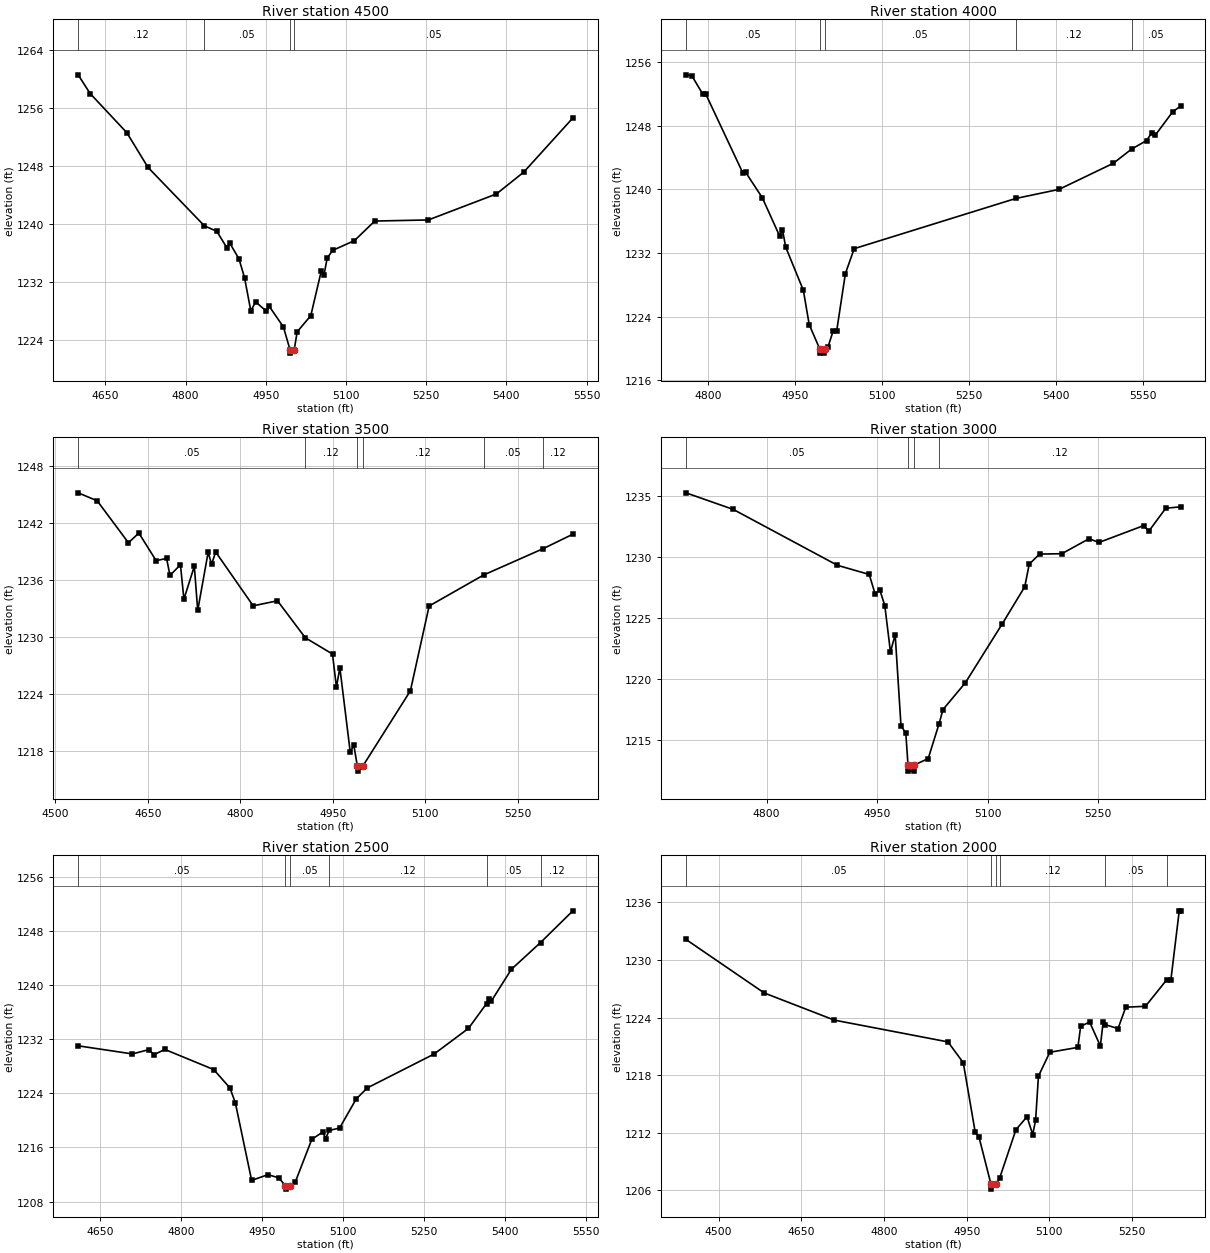
Type RM Length L Ch R = 1 ,4500    ,500,500,500
BEGIN DESCRIPTION:
MAGILL CREEK 9.0
END DESCRIPTION:
XS GIS Cut Line= 3
      2793505.69     10285253.15       2793398.9     10284866.63
      2793505.68     10284353.12
#Sta/Elev= 30
    4599 1260.54  4621.4 1257.96  4690.1 1252.55  4729.6 1247.77  4835.1  1239.7
  4858.4 1238.94  4877.3 1236.66  4882.5 1237.33  4899.9 1235.13  4910.3 1232.53
    4922 1227.96    4931  1229.2  4951.2 1227.91  4956.4 1228.59  4982.9 1225.76
  4995.2 1222.63  4995.7 1222.13  5003.3 1222.63  5008.7 1225.07  5034.2  1227.3
  5053.7 1233.42  5058.8  1232.9  5064.9 1235.25  5075.1 1236.31  5115.9 1237.66
  5153.9 1240.36  5254.1 1240.51  5381.5  1244.1  5432.6 1247.11  5524.5 1254.59
#Mann= 4 ,-1 , 0
    4599     .12       0  4835.1     .05       0  4995.2     .05       0
  5003.3     .05       0
Bank Sta=4995.2,5003.3
XS Rating Curve= 0 ,0
Exp/Cntr=0.3,0.1

Type RM Length L Ch R = 1 ,4000    ,500,500,500
BEGIN DESCRIPTION:
MAGILL CREEK 8.0
END DESCRIPTION:
XS GIS Cut Line= 3
      2793855.69     10285153.08      2793891.55       10284918.
      2793555.71     10284403.15
#Sta/Elev= 30
  4762.2 1254.41  4772.3  1254.3  4791.4 1251.96  4796.4 1251.98    4860 1242.11
    4865 1242.16  4893.7 1238.97  4923.5 1234.17  4928.5 1234.96  4934.1 1232.75
  4964.5 1227.33  4974.6 1223.01  4992.9 1219.93  4993.4 1219.43  5000.7 1219.43
  5001.2 1219.93  5006.7 1220.14  5015.8 1222.21  5021.8 1222.15  5036.9 1229.42
  5052.1 1232.56  5330.6 1238.87    5405 1240.01  5498.6 1243.29    5530 1245.07
  5555.9 1246.15    5565 1247.14    5571 1246.83  5601.2 1249.79  5614.7 1250.47
#Mann= 5 ,-1 , 0
  4762.2     .05       0  4992.9     .05       0  5001.2     .05       0
  5330.6     .12       0    5530     .05       0
Bank Sta=4992.9,5001.2
XS Rating Curve= 0 ,0
Exp/Cntr=0.3,0.1

Type RM Length L Ch R = 1 ,3500    ,500,500,500
BEGIN DESCRIPTION:
MAGILL CREEK 7.0
END DESCRIPTION:
XS GIS Cut Line= 3
      2794155.68     10285203.12      2794359.91     10284787.71
      2794305.68     10284453.07
#Sta/Elev= 30
  4537.1 1245.13    4568 1244.29  4618.6 1239.88  4635.5  1240.9  4663.5    1238
  4680.4 1238.23    4686 1236.45  4702.9 1237.57  4708.5 1233.94  4725.4 1237.41
  4730.9 1232.76  4747.8 1238.88  4753.4 1237.62    4760 1238.91  4820.8 1233.25
  4860.2 1233.78  4905.3 1229.89  4949.4 1228.18  4955.7  1224.7  4961.3 1226.74
  4978.2 1217.83  4983.8 1218.65  4989.7 1216.37  4990.2 1215.87  4998.2 1216.37
  5075.6 1224.31    5106 1233.23  5194.3 1236.49  5290.5 1239.25    5339 1240.78
#Mann= 6 ,-1 , 0
  4537.1     .05       0  4905.3     .12       0  4989.7     .07       0
  4998.2     .12       0  5194.3     .05       0  5290.5     .12       0
Bank Sta=4989.7,4998.2
XS Rating Curve= 0 ,0
Exp/Cntr=0.3,0.1

Type RM Length L Ch R = 1 ,3000    ,500,500,500
BEGIN DESCRIPTION:
MAGILL CREEK 6.0
END DESCRIPTION:
XS GIS Cut Line= 3
       2794655.7     10285103.09      2794849.94     10284862.25
      2794805.68     10284503.07
#Sta/Elev= 30
  4690.6 1235.24  4754.8 1233.88  4896.1  1229.3  4939.3 1228.55  4947.2 1226.96
  4953.7 1227.28  4960.4    1226  4968.1  1222.2  4974.5 1223.61  4982.4 1216.14
  4988.9 1215.56  4991.9 1212.93  4992.4 1212.43    5000 1212.43  5000.5 1212.93
  5019.3 1213.46  5033.9 1216.28  5039.4 1217.48  5069.7 1219.67    5120 1224.52
  5150.3 1227.54  5156.4 1229.39  5170.4 1230.22  5200.6 1230.25  5237.6 1231.48
    5251 1231.17  5311.5 1232.55  5318.7  1232.1  5341.7 1233.98  5361.9 1234.09
#Mann= 4 ,-1 , 0
  4690.6     .05       0  4991.9     .05       0  5000.5     .05       0
  5033.9     .12       0
Bank Sta=4991.9,5000.5
XS Rating Curve= 0 ,0
Exp/Cntr=0.3,0.1

Type RM Length L Ch R = 1 ,2500    ,500,500,500
BEGIN DESCRIPTION:
MAGILL CREEK 5.0
END DESCRIPTION:
XS GIS Cut Line= 3
      2795305.68     10285303.11      2795335.24     10284914.23
      2795455.68     10284403.13
#Sta/Elev= 30
    4610 1231.04  4710.3 1229.84  4740.4 1230.47  4750.4 1229.74  4770.5  1230.5
  4860.7 1227.53  4890.8 1224.81  4900.8 1222.59  4930.9 1211.13    4961 1211.98
  4981.1 1211.51  4993.4 1210.34  4993.9 1209.84  5002.7 1210.34  5011.4 1210.84
  5042.2 1217.21  5062.5 1218.29  5067.6 1217.32  5074.4 1218.52  5093.6 1218.88
  5124.4 1223.19    5145 1224.82  5268.3 1229.82    5332 1233.62  5365.4 1237.29
  5369.2 1238.01  5374.3 1237.67  5411.5 1242.37  5465.3 1246.32  5525.1 1251.01
#Mann= 6 ,-1 , 0
    4610     .05       0  4993.4     .05       0  5002.7     .05       0
  5074.4     .12       0  5365.4     .05       0  5465.3     .12       0
Bank Sta=4993.4,5002.7
XS Rating Curve= 0 ,0
Exp/Cntr=0.3,0.1

Type RM Length L Ch R = 1 ,2000    ,500,500,500
BEGIN DESCRIPTION:
MAGILL CREEK 4.0
END DESCRIPTION:
XS GIS Cut Line= 3
       2795455.7      10285403.1      2795822.14     10284980.69
      2795905.69     10284653.08
#Sta/Elev= 30
  4440.8 1232.14  4582.8 1226.56    4710 1223.73  4916.1 1221.46  4943.8 1219.29
  4965.5 1212.03  4972.1 1211.59  4994.1 1206.62  4994.6 1206.12  5003.6 1206.62
  5009.8 1207.28  5039.3 1212.31  5059.4 1213.67  5069.7 1211.81    5075  1213.3
  5080.1 1217.89  5100.7 1220.38  5151.6 1220.89  5156.7 1223.08  5172.9 1223.54
  5192.4 1221.04  5197.6 1223.57  5201.7 1223.25  5224.5 1222.85  5238.5 1225.08
  5274.2 1225.17  5312.9 1227.94  5320.2 1227.87  5335.5 1235.12  5338.1 1235.12
#Mann= 6 ,-1 , 0
  4440.8     .05       0  4994.1     .03       0  5003.6     .05       0
  5009.8     .12       0  5201.7     .05       0  5312.9     .12       0
Bank Sta=4994.1,5003.6
XS Rating Curve= 0 ,0
Exp/Cntr=0.3,0.1

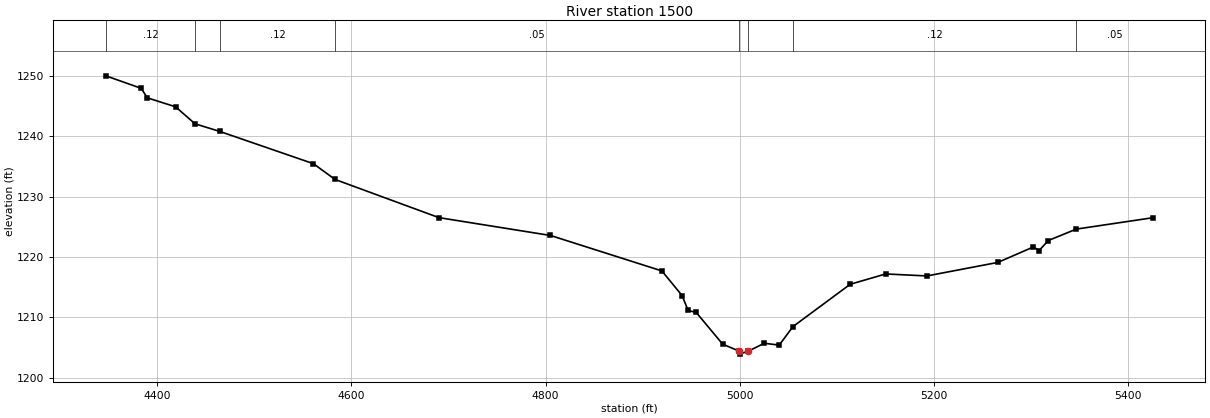
Type RM Length L Ch R = 1 ,1500    ,500,500,500
BEGIN DESCRIPTION:
MAGILL CREEK 3.0
END DESCRIPTION:
XS GIS Cut Line= 3
      2795705.72     10285653.08      2796229.99     10285263.78
       2796455.7     10284903.08
#Sta/Elev= 30
    4347 1249.99  4383.5 1247.92  4389.7 1246.35  4418.9 1244.86  4438.9 1242.05
  4464.5 1240.78  4560.8 1235.45  4583.1 1232.84  4690.1 1226.52  4804.9 1223.57
  4919.7  1217.7  4940.5 1213.62  4946.7 1211.16  4955.1 1210.82  4982.2 1205.59
  4999.2 1204.43  4999.7 1203.93  5008.8 1204.43  5025.2 1205.73  5040.5 1205.42
  5054.7 1208.49  5113.6 1215.49  5150.2  1217.2  5192.6 1216.87  5265.7 1219.11
  5302.3 1221.67  5308.2 1221.08  5317.6 1222.73  5346.4 1224.62  5425.5 1226.51
#Mann= 8 ,-1 , 0
    4347     .12       0  4438.9     .05       0  4464.5     .12       0
  4583.1     .05       0  4999.2     .05       0  5008.8     .05       0
  5054.7     .12       0  5346.4     .05       0
Bank Sta=4999.2,5008.8
XS Rating Curve= 0 ,0
Exp/Cntr=0.3,0.1