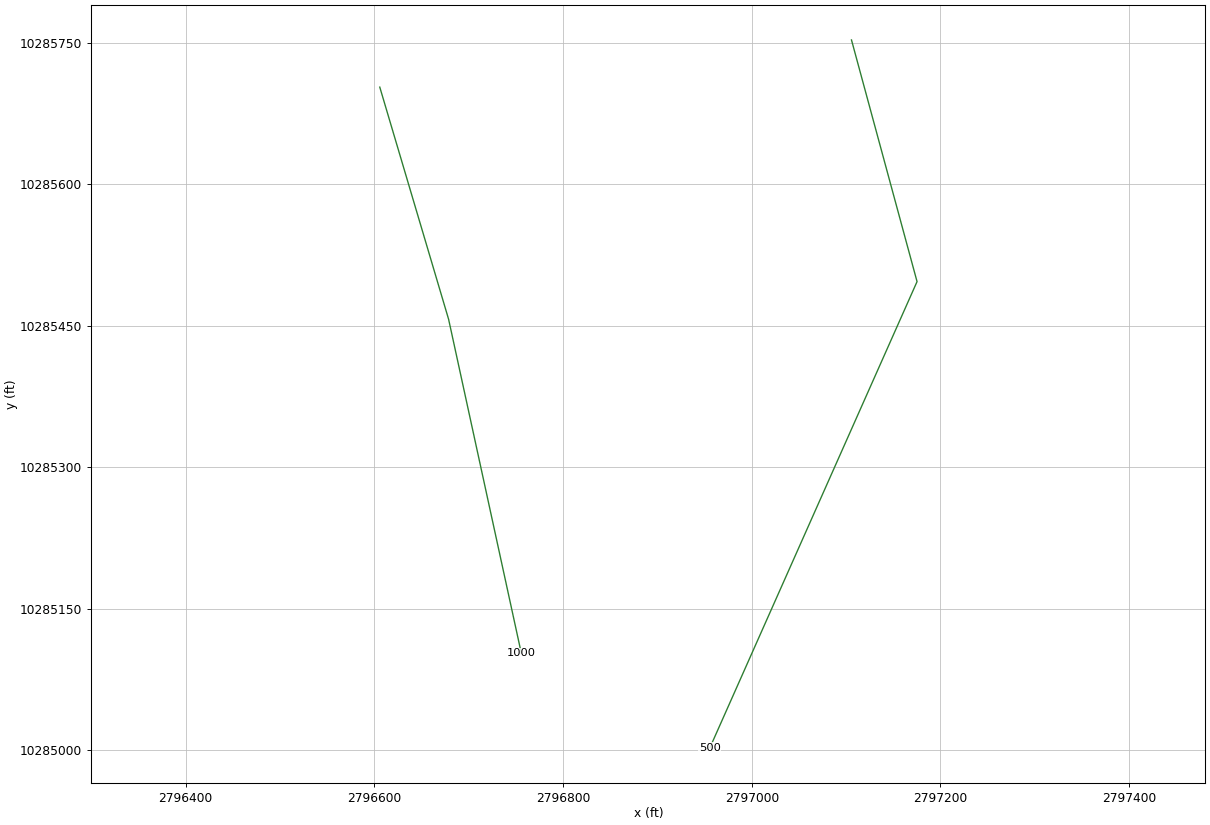
HEC-RAS study MAGILL CREEK.prj: MAGILL CREEK Base Level Engineering

--- MAGILL CREEK.g01 (geometry) --- (continued)

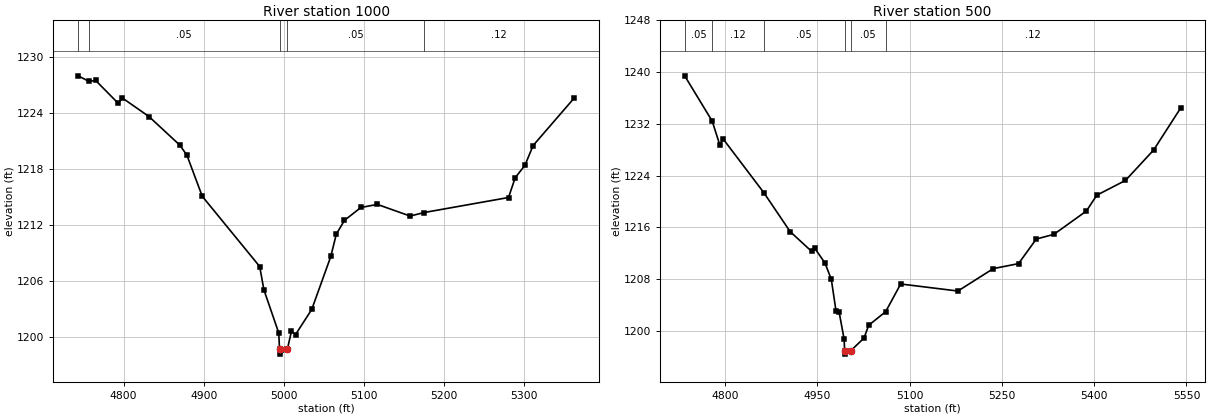
Type RM Length L Ch R = 1 ,1000    ,500,500,500
BEGIN DESCRIPTION:
MAGILL CREEK 2.0
END DESCRIPTION:
XS GIS Cut Line= 3
      2796605.68     10285703.13      2796678.62     10285457.11
      2796755.69      10285103.1
#Sta/Elev= 30
  4743.4 1227.98  4756.8 1227.38  4765.2 1227.48  4793.3 1225.03  4798.5  1225.6
  4831.7 1223.61  4870.2 1220.54    4879 1219.47  4898.2 1215.05  4969.9 1207.51
  4975.1 1205.02  4993.7 1200.37  4994.6 1198.61  4995.1 1198.11  5004.3 1198.61
  5009.5 1200.55  5014.6 1200.21  5034.8  1202.9  5058.6 1208.59  5065.5 1210.99
  5075.7 1212.47  5096.2 1213.85  5116.7 1214.18  5157.6 1212.93  5175.2 1213.31
  5280.4 1214.92  5288.7 1217.04  5300.9 1218.38  5311.1  1220.5  5362.3 1225.59
#Mann= 5 ,-1 , 0
  4743.4     .12       0  4756.8     .05       0  4994.6     .05       0
  5004.3     .05       0  5175.2     .12       0
Bank Sta=4994.6,5004.3
XS Rating Curve= 0 ,0
Exp/Cntr=0.3,0.1

Type RM Length L Ch R = 1 ,500     ,0,0,0
BEGIN DESCRIPTION:
MAGILL CREEK 1.0
END DESCRIPTION:
XS GIS Cut Line= 3
      2797105.68     10285753.14      2797175.17       10285497.
      2796955.67     10285003.08
#Sta/Elev= 30
  4734.6 1239.43  4779.3 1232.43  4791.8  1228.7  4796.9 1229.69  4863.5 1221.32
    4906 1215.33  4940.7 1212.29  4945.9 1212.77  4962.6 1210.47  4972.9 1207.94
  4980.5 1203.06  4985.7 1202.82  4993.7 1198.69  4994.5 1196.88    4995 1196.38
  5004.3 1196.88  5026.1 1198.88  5033.6 1200.84  5061.2 1202.95  5085.6 1207.23
  5178.6 1206.14  5236.1 1209.61  5277.1 1210.38  5305.9 1214.18  5334.6 1214.91
  5387.3 1218.51  5404.4 1220.97  5450.9 1223.25  5496.7 1227.96  5540.5 1234.44
#Mann= 6 ,-1 , 0
  4734.6     .05       0  4779.3     .12       0  4863.5     .05       0
  4994.5     .05       0  5004.3     .05       0  5061.2     .12       0
Bank Sta=4994.5,5004.3
XS Rating Curve= 0 ,0
Exp/Cntr=0.3,0.1

Chan Stop Cuts=-1
Use User Specified Reach Order=0
Composite Channel Slope=5