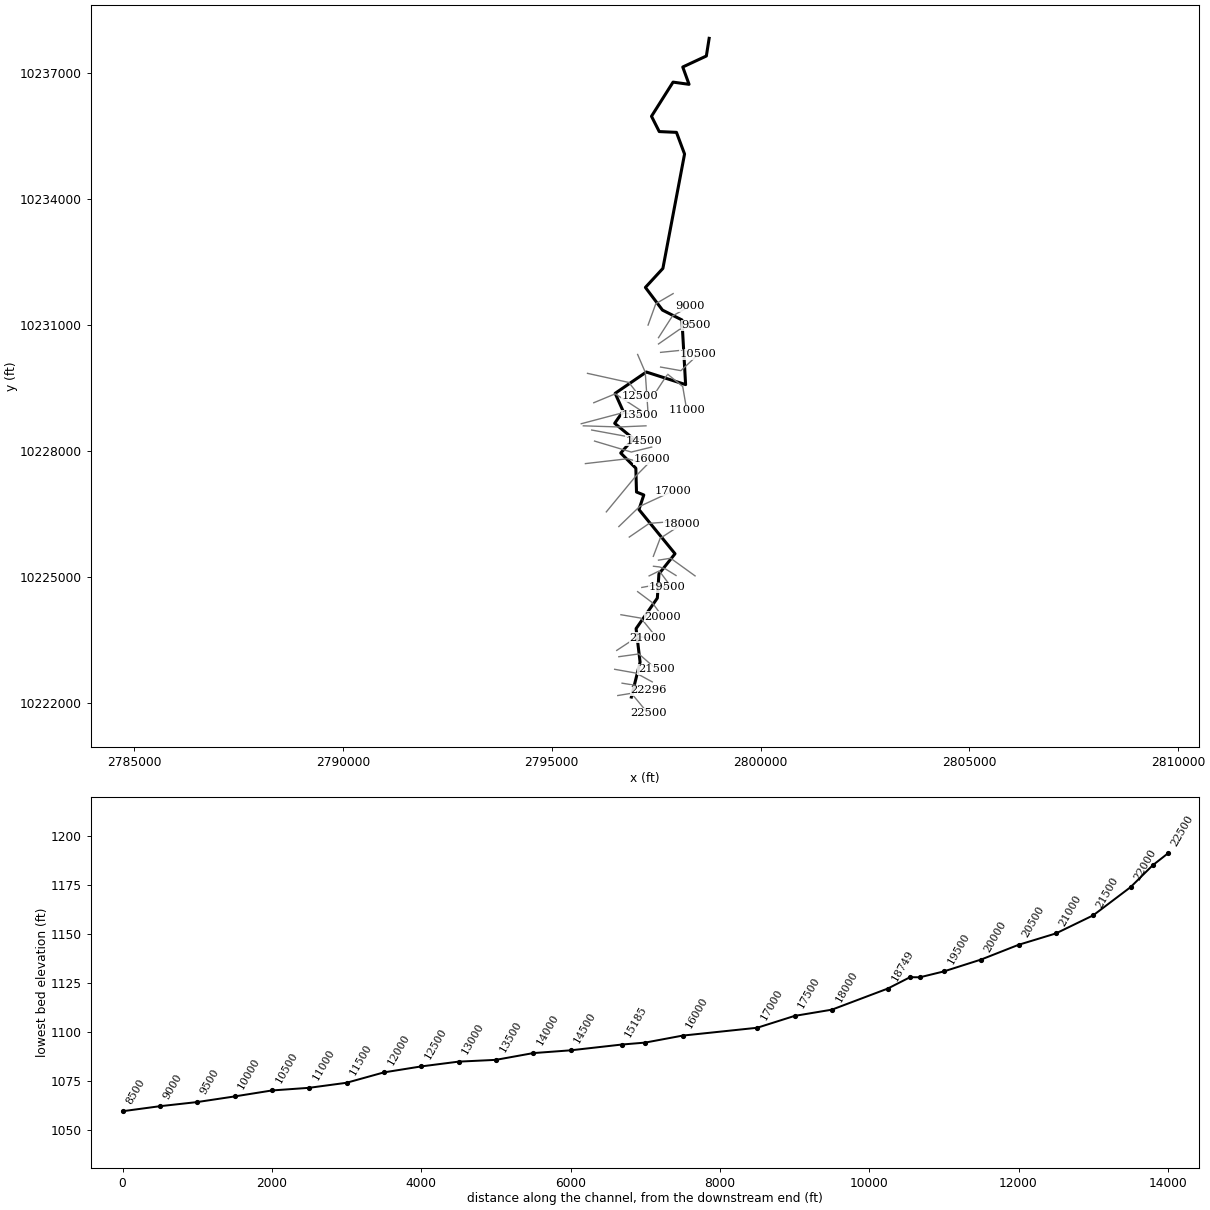
--- MARCHISON CREEK.prj (project) ---

Proj Title=MARCHISON CREEK Base Level Engineering
Current Plan=p01
Default Exp/Contr=0.3,0.1
English Units
Geom File=g01
Flow File=f01
Plan File=p01
Y Axis Title=Elevation
X Axis Title(PF)=Main Channel Distance
X Axis Title(XS)=Station
BEGIN DESCRIPTION:
MARCHISON CREEK
END DESCRIPTION:
DSS Export Rating Curves= 0
DSS Export Rating Curve Sorted= 0
DSS Export Volume Flow Curves= 0
DXF OffsetX= 0
DXF OffsetY= 0
DXF ScaleX= 1
DXF ScaleY= 10

--- MARCHISON CREEK.p01 (plan) ---

Plan Title=Multiple Run
Short Identifier=Multiple
Geom File=g01
Flow File=f01
Subcritical Flow
K Sum by GR= 0
Std Step Tol= 0.01
Critical Tol= 0.01
Num of Std Step Trials= 20
Max Error Tol= 0.3
Flow Tol Ratio= 0.001
Split Flow NTrial= 30
Split Flow Tol= 0.02
Split Flow Ratio= 0.02
Log Output Level= 0
Friction Slope Method= 1
Unsteady Friction Slope Method= 2
Unsteady Bridges Friction Slope Method= 1
Parabolic Critical Depth
Global Vel Dist=  1 , 1 , 1
Global Log Level= 0
CheckData=True
Encroach Param= -1, 0, 0, 0
BEGIN DESCRIPTION:
Multiple Run
END DESCRIPTION:

--- MARCHISON CREEK.f01 (steady flow) ---

Flow Title=Multiple
Number of Profiles=7
Profile Names=10-year,25-year,50-year,1pct_min,100-year,1pct_plu,500-year
River Rch & RM= MARCHISON CREEK,Reach-1,22500
     132     198     268     158     347     762     489
River Rch & RM= MARCHISON CREEK,Reach-1,18000
     415     668     967     565    1296    2969    1791
River Rch & RM= MARCHISON CREEK,Reach-1,13500
     532     873    1204     894    1619    2931    2227
River Rch & RM= MARCHISON CREEK,Reach-1,11000
     729    1221    1686    1007    2288    5199    3135
River Rch & RM= MARCHISON CREEK,Reach-1,7500
     791    1333    1798    1053    2442    5660    3339
River Rch & RM= MARCHISON CREEK,Reach-1,5500
     953    1626    2194    1326    2995    6767    4087
River Rch & RM= MARCHISON CREEK,Reach-1,3000
    1075    1842    2607    1864    3581    6881    4879
Boundary for River Rch & Prof#=MARCHISON CREEK,Reach-1,1
Up Type=0
Dn Type=3
Dn Slope=0.005
Boundary for River Rch & Prof#=MARCHISON CREEK,Reach-1,2
Up Type=0
Dn Type=3
Dn Slope=0.005
Boundary for River Rch & Prof#=MARCHISON CREEK,Reach-1,3
Up Type=0
Dn Type=3
Dn Slope=0.005
Boundary for River Rch & Prof#=MARCHISON CREEK,Reach-1,4
Up Type=0
Dn Type=3
Dn Slope=0.005
Boundary for River Rch & Prof#=MARCHISON CREEK,Reach-1,5
Up Type=0
Dn Type=3
Dn Slope=0.005
Boundary for River Rch & Prof#=MARCHISON CREEK,Reach-1,6
Up Type=0
Dn Type=3
Dn Slope=0.005
Boundary for River Rch & Prof#=MARCHISON CREEK,Reach-1,7
Up Type=0
Dn Type=3
Dn Slope=0.005

--- MARCHISON CREEK.g01 (geometry) ---

Geom Title=Existing Conditions
Program Version=4.10

River Reach=MARCHISON CREEK ,Reach-1
Reach XY= 30
        2796906.       10222142.      2797114.25       10222975.
       2797018.5       10223772.      2797527.75       10224500.
      2797565.25       10225075.      2797950.75       10225556.
      2797087.25       10226609.      2797203.75       10226956.
      2797028.75       10227026.       2797012.5       10227594.
       2796650.5       10227955.        2796954.       10228296.
        2796506.       10228663.        2796709.       10228952.
       2796517.5       10229377.      2797263.25       10229885.
      2798204.25       10229585.       2798116.5       10231125.
      2797650.75       10231360.       2797241.5       10231900.
      2797660.25       10232353.        2798179.       10235078.
      2797985.25       10235594.      2797572.75       10235613.
       2797387.5       10235977.        2797904.       10236791.
      2798286.75       10236738.      2798135.75       10237151.
      2798700.75       10237413.      2798767.75       10237834.

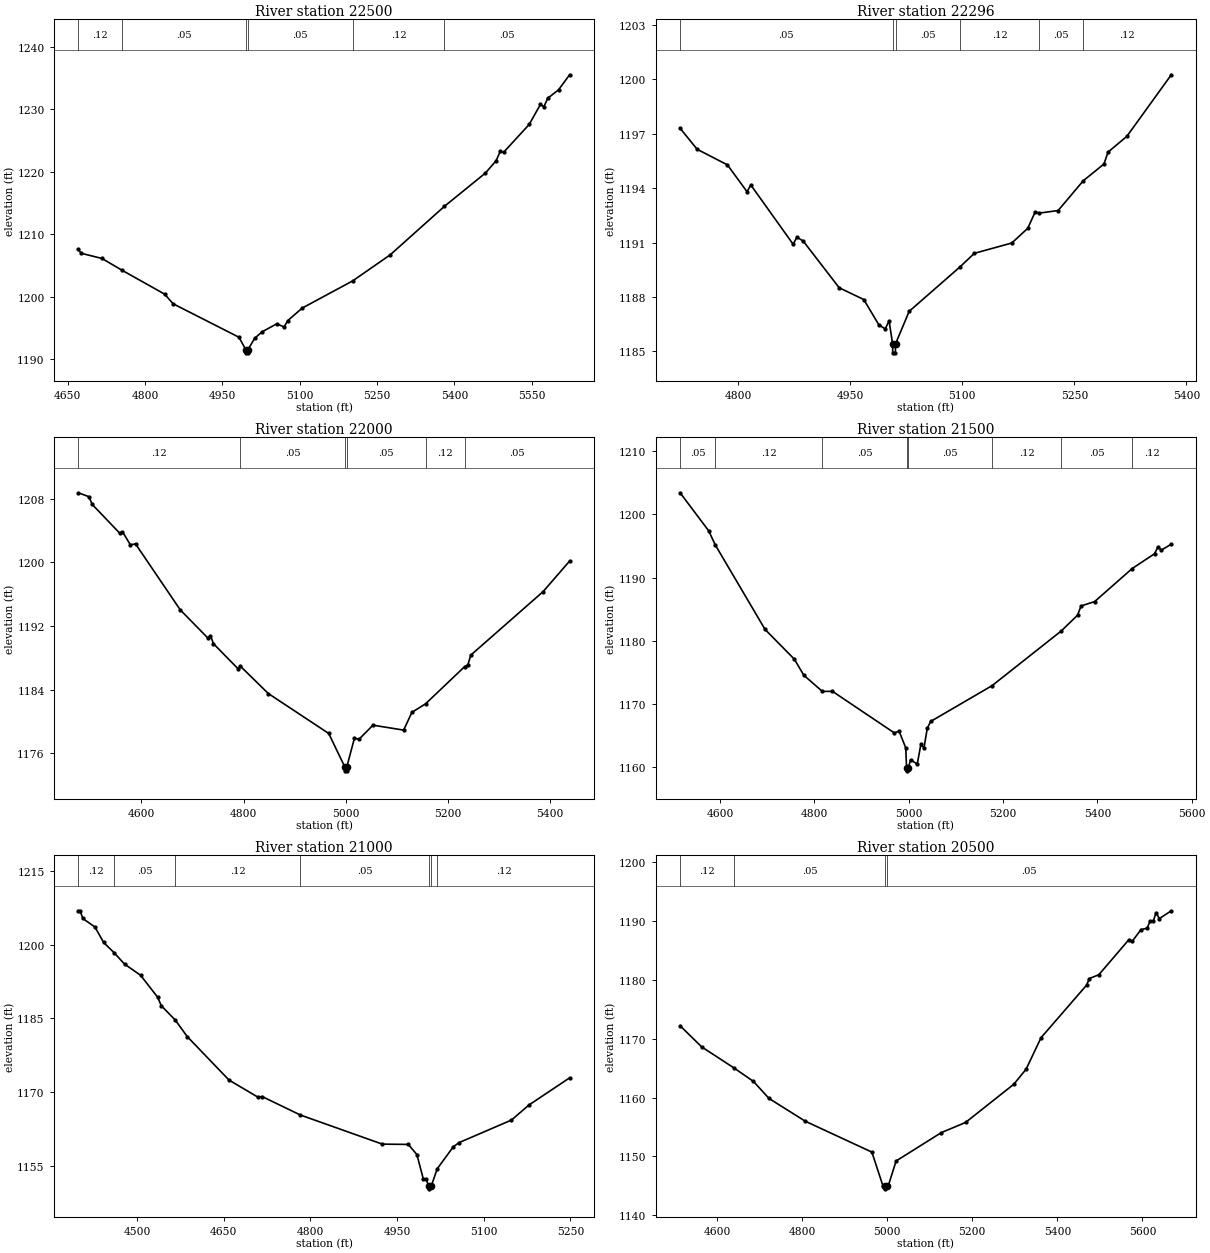
Type RM Length L Ch R = 1 ,22500   ,204,204,204
BEGIN DESCRIPTION:
MARCHISON CREEK 44.0
END DESCRIPTION:
XS GIS Cut Line= 3
      2796580.69     10222178.11      2796905.64     10222231.44
      2797305.71     10221753.09
#Sta/Elev= 30
  4670.7 1207.58  4675.8 1206.94  4716.3 1206.11  4755.3 1204.22  4837.9  1200.4
  4854.5 1198.85  4982.1  1193.5  4995.5  1191.5  4995.7    1191  4999.2    1191
  4999.5  1191.5  5012.6 1193.32  5026.9 1194.36  5055.6 1195.65  5069.9 1195.13
  5076.4 1196.13    5105 1198.17  5202.6 1202.51  5275.5 1206.68  5380.7 1214.45
  5460.3 1219.78  5481.1 1221.76  5488.9 1223.23  5495.4 1223.09  5545.3 1227.57
    5567 1230.77  5573.5 1230.37  5581.3 1231.76  5602.1  1233.1  5623.6 1235.51
#Mann= 6 ,-1 , 0
  4670.7     .12       0  4755.3     .05       0  4995.5     .03       0
  4999.5     .05       0  5202.6     .12       0  5380.7     .05       0
Bank Sta=4995.5,4999.5
XS Rating Curve= 0 ,0
Exp/Cntr=0.3,0.1

Type RM Length L Ch R = 1 ,22296   ,296,296,296
BEGIN DESCRIPTION:
Mapping XS 46d54ce4
END DESCRIPTION:
XS GIS Cut Line= 3
       2796683.2     10222472.59      2797004.42      10222420.5
      2797316.29     10222307.88
#Sta/Elev= 30
  4722.7 1197.31  4745.5 1196.15    4786 1195.29  4812.2 1193.81  4817.3 1194.18
  4873.9 1190.91  4878.9  1191.3  4887.3 1191.09  4935.5 1188.51  4968.4 1187.86
  4988.6 1186.46  4997.1 1186.24  5002.2 1186.69  5006.9 1185.42  5007.1 1184.92
  5010.6 1184.92  5010.9 1185.42  5029.1 1187.21  5096.5 1189.64  5116.3 1190.41
  5166.4 1190.98  5187.7 1191.79  5197.7  1192.7  5203.2 1192.63  5228.3 1192.77
  5261.9 1194.41  5289.7 1195.34    5295 1195.99  5320.4 1196.87  5379.7 1200.26
#Mann= 6 ,-1 , 0
  4722.7     .05       0  5006.9     .03       0  5010.9     .05       0
  5096.5     .12       0  5203.2     .05       0  5261.9     .12       0
Bank Sta=5006.9,5010.9
XS Rating Curve= 0 ,0
Exp/Cntr=0.3,0.1

Type RM Length L Ch R = 1 ,22000   ,500,500,500
BEGIN DESCRIPTION:
MARCHISON CREEK 43.0
END DESCRIPTION:
XS GIS Cut Line= 3
      2796505.64     10222803.12       2797020.7     10222711.76
      2797405.69     10222503.11
#Sta/Elev= 30
  4476.9 1208.76  4497.3 1208.27    4504 1207.29    4558 1203.66  4563.1 1203.86
  4578.5 1202.23  4588.7 1202.33  4676.2 1194.04  4730.2  1190.5  4735.3 1190.81
    4741  1189.8  4789.3 1186.63  4793.5 1186.98  4848.4 1183.53  4966.6 1178.51
    4998 1174.31  4998.2 1173.81  5001.7 1173.81    5002 1174.31    5017 1177.93
  5025.7 1177.77  5053.2 1179.55  5113.2 1178.93  5129.3 1181.16    5156 1182.23
  5232.4  1186.9  5238.7  1187.1  5244.5 1188.35  5386.1 1196.34  5437.9 1200.18
#Mann= 6 ,-1 , 0
  4476.9     .12       0  4793.5     .05       0    4998     .03       0
    5002     .05       0    5156     .12       0  5232.4     .05       0
Bank Sta=4998,5002
XS Rating Curve= 0 ,0
Exp/Cntr=0.3,0.1

Type RM Length L Ch R = 1 ,21500   ,500,500,500
BEGIN DESCRIPTION:
MARCHISON CREEK 42.0
END DESCRIPTION:
XS GIS Cut Line= 3
      2796605.64     10223103.11      2797086.12     10223169.11
      2797505.71     10222803.09
#Sta/Elev= 30
    4515 1203.42  4575.6 1197.41  4589.9 1195.14  4695.2 1181.82  4757.3 1177.12
  4777.5 1174.57  4816.8 1172.02  4838.1 1172.04  4969.3 1165.47  4979.4 1165.75
  4993.6  1163.1  4995.3 1159.97  4995.5 1159.47  4999.3 1159.97  5003.8 1161.22
    5018 1160.54  5025.6 1163.64  5032.3  1163.1  5039.2 1166.19  5046.5 1167.28
  5176.8 1172.94  5323.4 1181.58  5357.9 1184.06  5365.5 1185.54    5394 1186.21
  5473.6 1191.43  5521.2 1193.78  5528.8  1194.9  5535.4 1194.34  5556.8  1195.3
#Mann= 8 ,-1 , 0
    4515     .05       0  4589.9     .12       0  4816.8     .05       0
  4995.3     .05       0  4999.3     .05       0  5176.8     .12       0
  5323.4     .05       0  5473.6     .12       0
Bank Sta=4995.3,4999.3
XS Rating Curve= 0 ,0
Exp/Cntr=0.3,0.1

Type RM Length L Ch R = 1 ,21000   ,500,500,500
BEGIN DESCRIPTION:
MARCHISON CREEK 41.0
END DESCRIPTION:
XS GIS Cut Line= 3
      2796555.68     10223253.11      2797058.86     10223583.21
      2797305.64     10223553.12
#Sta/Elev= 30
  4398.2 1206.97  4401.2 1206.97  4405.8  1205.4  4426.8 1203.66  4441.9  1200.5
  4460.2 1198.39  4478.1 1196.09  4505.8 1193.82  4535.3 1189.35  4541.7  1187.6
  4565.8 1184.69  4586.6 1181.31  4658.9 1172.44  4709.2 1168.94  4716.2 1169.08
  4782.5 1165.31  4924.4 1159.37  4969.4 1159.31  4984.2 1157.24  4995.3 1152.26
    5000 1152.26  5004.9 1150.75  5005.1 1150.25  5008.9 1150.75  5019.5 1154.36
  5047.2 1158.82  5057.2 1159.68  5147.9 1164.28  5178.1 1167.34  5248.6 1172.89
#Mann= 7 ,-1 , 0
  4398.2     .12       0  4460.2     .05       0  4565.8     .12       0
  4782.5     .05       0  5004.9     .05       0  5008.9     .05       0
  5019.5     .12       0
Bank Sta=5004.9,5008.9
XS Rating Curve= 0 ,0
Exp/Cntr=0.3,0.1

Type RM Length L Ch R = 1 ,20500   ,500,500,500
BEGIN DESCRIPTION:
MARCHISON CREEK 40.0
END DESCRIPTION:
XS GIS Cut Line= 3
      2796655.72     10224103.11      2797135.52     10224022.04
      2797555.68     10223503.11
#Sta/Elev= 30
  4513.4 1172.21  4564.1 1168.62  4639.2 1165.07  4685.8 1162.74  4722.4 1159.84
  4807.5 1155.97  4964.1 1150.71    4990 1144.98  4995.5 1144.96  4995.8 1144.46
  4999.5 1144.96  5002.5 1144.96    5021  1149.2  5127.3 1154.03  5184.1 1155.75
  5297.6 1162.26  5326.4 1164.81  5361.6 1170.18  5468.7 1179.13  5475.1 1180.25
  5497.4 1180.89  5567.8 1186.85  5575.7 1186.57  5596.6 1188.59  5610.9  1188.8
  5617.4 1189.98  5625.3 1189.98  5631.8 1191.46  5639.7 1190.45  5667.7 1191.78
#Mann= 4 ,-1 , 0
  4513.4     .12       0  4639.2     .05       0  4995.5     .03       0
  4999.5     .05       0
Bank Sta=4995.5,4999.5
XS Rating Curve= 0 ,0
Exp/Cntr=0.3,0.1

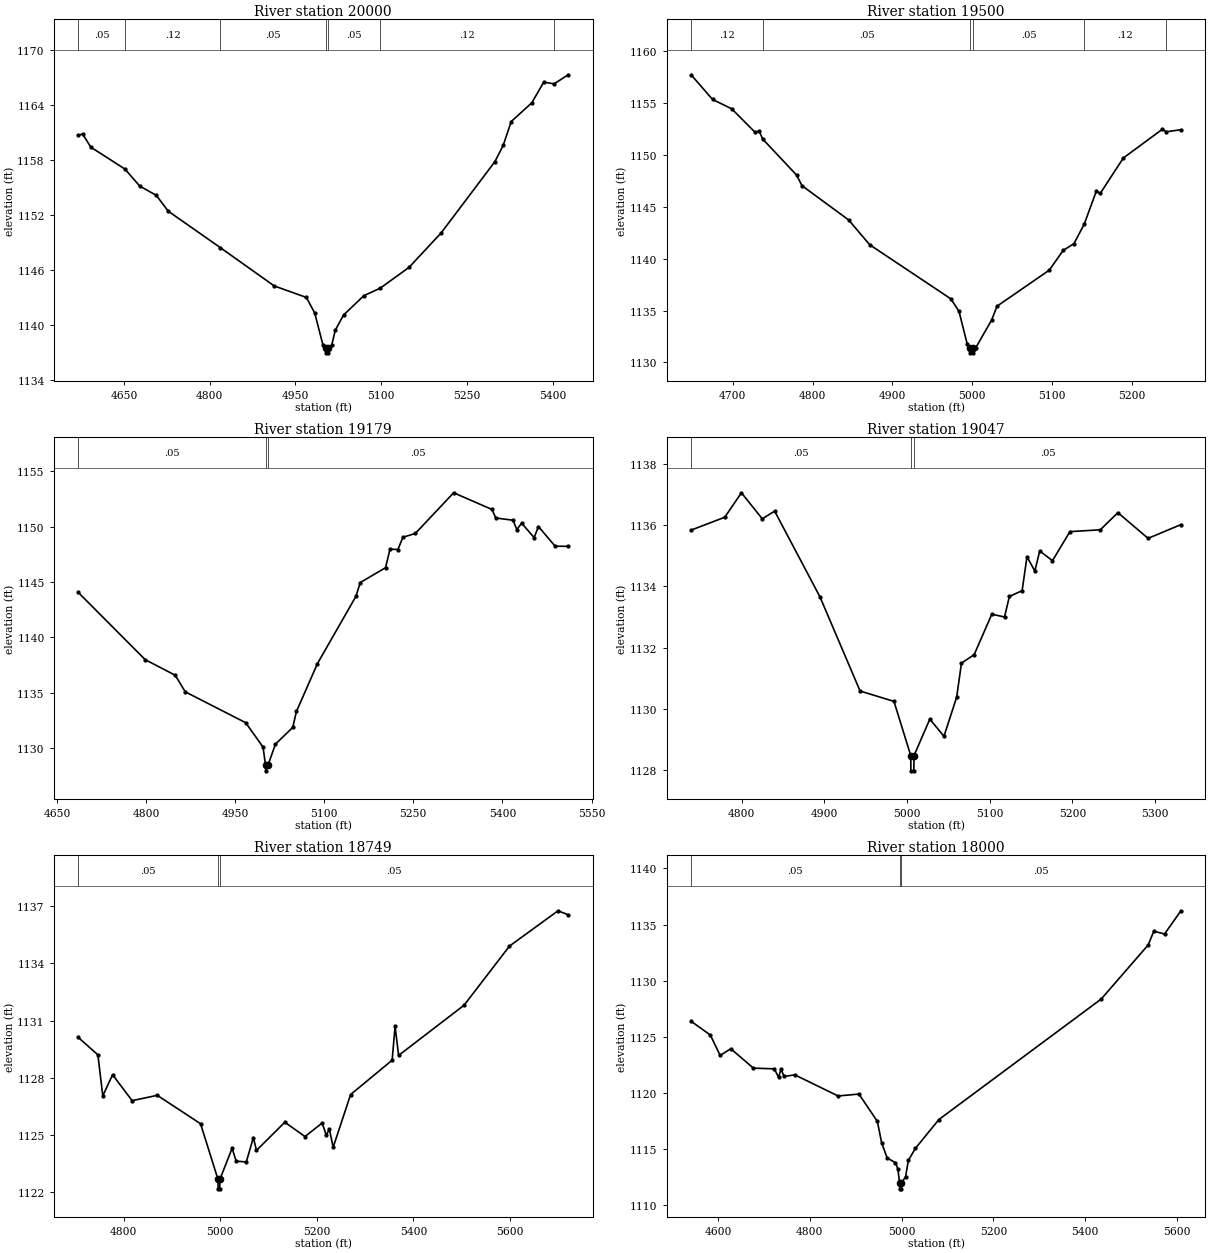
Type RM Length L Ch R = 1 ,20000   ,500,500,500
BEGIN DESCRIPTION:
MARCHISON CREEK 39.0
END DESCRIPTION:
XS GIS Cut Line= 3
      2797055.72     10224653.09      2797400.79     10224396.19
      2797655.68     10224053.11
#Sta/Elev= 30
  4569.8 1160.65  4577.1 1160.82  4591.7 1159.37  4651.5 1156.98  4677.2 1155.14
  4706.4 1154.12  4727.2  1152.4  4818.5 1148.43  4912.8 1144.26  4969.1 1143.01
  4983.7 1141.31  4998.3 1137.78    5003 1137.48  5003.3 1136.98  5006.8 1136.98
    5007 1137.48  5013.3 1137.78  5019.6 1139.44  5034.2  1141.1  5069.6  1143.2
  5098.4 1144.02  5148.9 1146.29  5205.2 1150.05  5299.1 1157.79  5313.7 1159.57
  5327.7 1162.16  5363.8  1164.2  5384.6 1166.45  5402.9 1166.26  5427.4 1167.25
#Mann= 7 ,-1 , 0
  4569.8     .05       0  4651.5     .12       0  4818.5     .05       0
    5003     .03       0    5007     .05       0  5098.4     .12       0
  5402.9     .05       0
Bank Sta=5003,5007
XS Rating Curve= 0 ,0
Exp/Cntr=0.3,0.1

Type RM Length L Ch R = 1 ,19500   ,321,321,321
BEGIN DESCRIPTION:
MARCHISON CREEK 38.0
END DESCRIPTION:
XS GIS Cut Line= 3
      2797155.66     10224753.11      2797502.12     10224815.87
      2797755.67     10224753.11
#Sta/Elev= 30
  4647.9 1157.75  4674.7 1155.37  4698.7 1154.47  4728.1 1152.19  4733.2 1152.32
  4737.4 1151.56    4780 1148.07  4786.7 1147.05  4845.2 1143.74  4871.5 1141.35
  4973.1 1136.13  4983.3 1134.93  4993.5  1131.8  4997.3 1131.42  4997.5 1130.92
    5001 1130.92  5001.3 1131.42  5004.4 1131.42  5024.3  1134.1  5030.9 1135.42
  5096.4  1138.9  5113.7  1140.8  5127.3 1141.46  5140.2 1143.35  5155.1 1146.49
  5160.3 1146.32  5189.1 1149.72  5237.9 1152.49    5243 1152.25  5261.2 1152.45
#Mann= 6 ,-1 , 0
  4647.9     .12       0  4737.4     .05       0  4997.3     .03       0
  5001.3     .05       0  5140.2     .12       0    5243     .05       0
Bank Sta=4997.3,5001.3
XS Rating Curve= 0 ,0
Exp/Cntr=0.3,0.1

Type RM Length L Ch R = 1 ,19179   ,132,132,132
BEGIN DESCRIPTION:
MARCHISON CREEK 37.0
END DESCRIPTION:
XS GIS Cut Line= 3
      2797330.71     10225028.12      2797573.32     10225146.89
      2797905.71     10224703.08
#Sta/Elev= 30
  4686.1 1144.05  4798.6 1137.98  4849.2 1136.57  4866.1 1135.07  4967.8 1132.28
    4997 1130.08  5001.3 1128.43  5001.5 1127.93  5005.3 1128.43  5017.9 1130.34
    5047 1131.85  5053.3  1133.3  5088.7 1137.63  5153.3 1143.69  5160.8 1144.95
  5203.3 1146.29  5210.8 1147.97  5224.1 1147.93  5232.5 1149.04  5253.3 1149.38
  5317.9 1153.06  5382.5 1151.55  5388.8 1150.78  5417.9 1150.58  5424.2 1149.74
  5432.5 1150.31  5453.4 1149.01  5460.7 1150.01  5488.8 1148.23  5510.7 1148.22
#Mann= 3 ,-1 , 0
  4686.1     .05       0  5001.3     .05       0  5005.3     .05       0
Bank Sta=5001.3,5005.3
XS Rating Curve= 0 ,0
Exp/Cntr=0.3,0.1

Type RM Length L Ch R = 1 ,19047   ,298,298,298
BEGIN DESCRIPTION:
Mapping XS 82953a4e
END DESCRIPTION:
XS GIS Cut Line= 4
       2797435.2      10225257.8      2797577.75     10225241.66
      2797722.99     10225193.25       2797975.1     10225037.69
#Sta/Elev= 30
  4738.6 1135.84  4779.3 1136.26  4799.5 1137.06  4824.7 1136.21  4839.7 1136.46
  4894.5 1133.66  4943.1 1130.58  4984.1 1130.24  5004.4 1128.47  5004.6 1127.97
  5008.1 1127.97  5008.4 1128.47  5027.5 1129.66  5044.6  1129.1    5060 1130.38
  5065.8 1131.49  5081.2 1131.77  5102.5 1133.09  5117.9    1133  5123.8 1133.67
  5139.2 1133.86  5145.1 1134.97  5154.6  1134.5  5160.5 1135.16  5175.9 1134.84
  5197.1 1135.79  5233.8 1135.85  5255.1 1136.41  5291.7 1135.57  5331.4 1136.02
#Mann= 3 ,-1 , 0
  4738.6     .05       0  5004.4     .05       0  5008.4     .05       0
Bank Sta=5004.4,5008.4
XS Rating Curve= 0 ,0
Exp/Cntr=0.3,0.1

Type RM Length L Ch R = 1 ,18749   ,749,749,749
BEGIN DESCRIPTION:
MARCHISON CREEK 36.0
END DESCRIPTION:
XS GIS Cut Line= 3
      2797555.66     10225403.11      2797845.75       10225449.
      2798430.67     10225028.12
#Sta/Elev= 30
  4706.3 1130.12  4746.8 1129.21  4756.9 1127.06  4777.2 1128.17  4817.7 1126.81
  4869.8 1127.09  4959.4  1125.6  4995.4 1122.69  4995.7 1122.19  4999.2 1122.19
  4999.4 1122.69  5024.7 1124.31  5033.2 1123.64  5054.1  1123.6  5068.8 1124.88
    5075  1124.2  5133.9 1125.68  5175.6 1124.93  5211.2 1125.64  5219.8 1124.99
    5226 1125.33    5234 1124.37  5270.1 1127.13  5356.1 1128.93  5362.2  1130.7
  5369.5 1129.18    5505 1131.81  5599.1 1134.91  5699.7 1136.76  5720.6 1136.55
#Mann= 3 ,-1 , 0
  4706.3     .05       0  4995.4     .05       0  4999.4     .05       0
Bank Sta=4995.4,4999.4
XS Rating Curve= 0 ,0
Exp/Cntr=0.3,0.1

Type RM Length L Ch R = 1 ,18000   ,500,500,500
BEGIN DESCRIPTION:
MARCHISON CREEK 35.0
END DESCRIPTION:
XS GIS Cut Line= 3
       2797431.2     10225493.98      2797594.76     10225922.53
      2798105.65     10226253.09
#Sta/Elev= 30
  4541.3 1126.38  4583.2 1125.15  4604.6 1123.33  4627.7 1123.93  4677.1  1122.2
  4722.3 1122.14  4731.9  1121.4  4737.3 1122.11  4743.7 1121.46  4767.4  1121.6
  4861.5 1119.72    4907 1119.89  4947.1 1117.45  4956.5 1115.53  4968.5 1114.19
  4986.6 1113.77  4991.9 1113.19  4995.6 1111.94  4995.9 1111.44  4999.4 1111.44
  4999.6 1111.94  5008.7 1112.54  5014.6 1113.97  5029.8 1115.04  5081.2 1117.62
  5434.8 1128.36  5537.1 1133.18  5549.5 1134.41  5572.8 1134.16  5608.5 1136.23
#Mann= 3 ,-1 , 0
  4541.3     .05       0  4995.6     .03       0  4999.6     .05       0
Bank Sta=4995.6,4999.6
XS Rating Curve= 0 ,0
Exp/Cntr=0.3,0.1

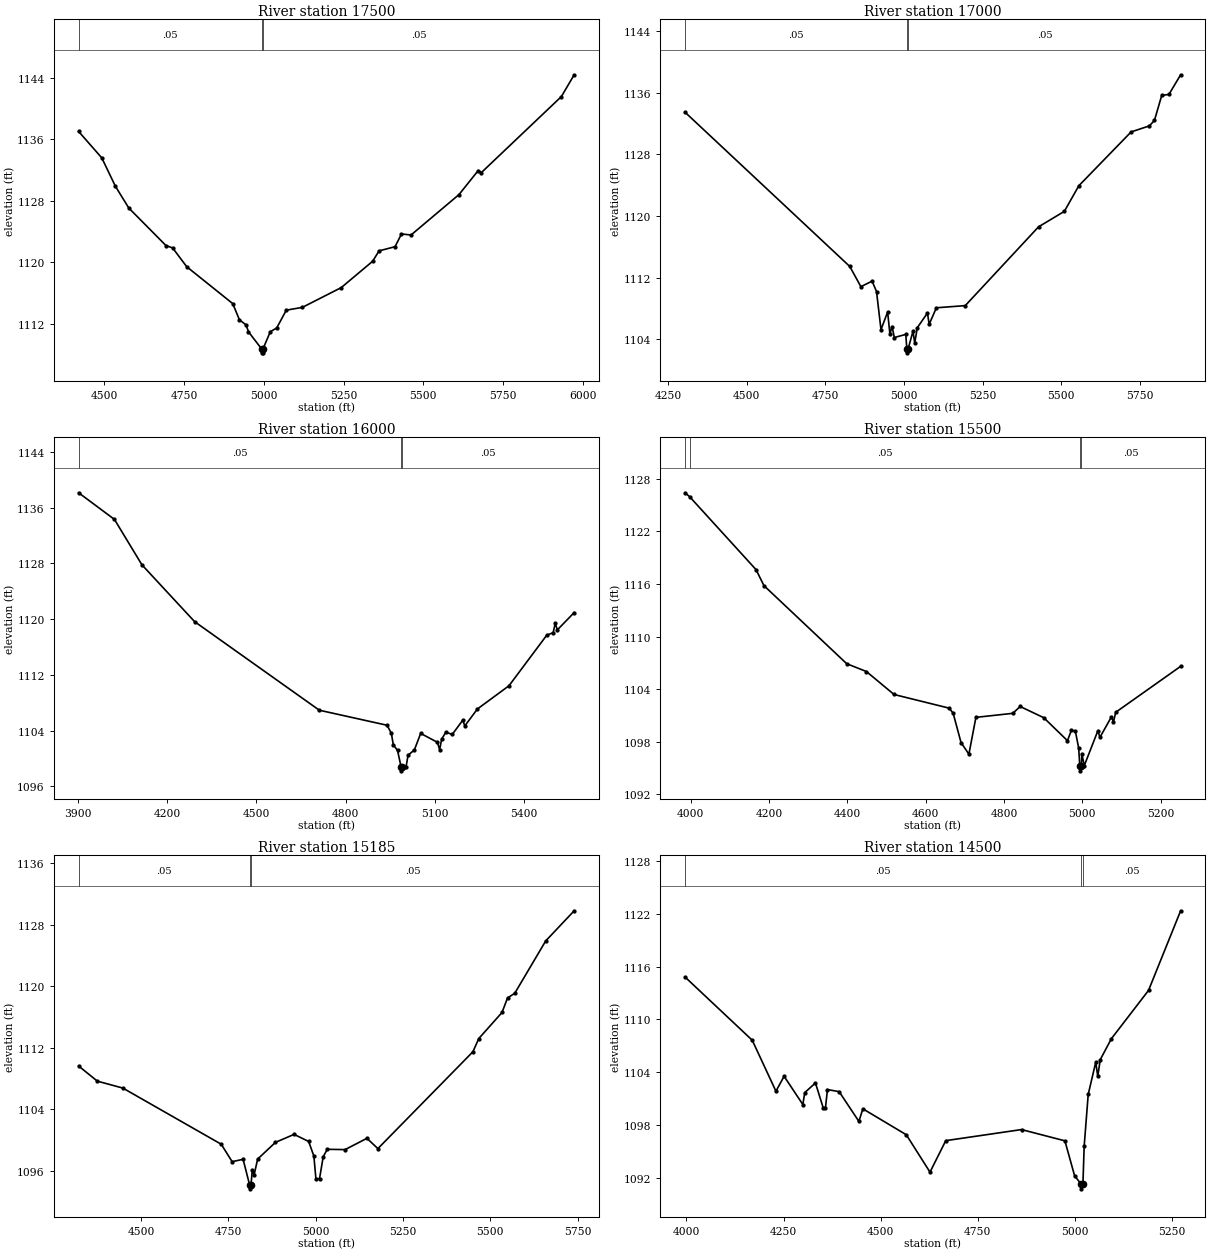
Type RM Length L Ch R = 1 ,17500   ,500,500,500
BEGIN DESCRIPTION:
MARCHISON CREEK 34.0
END DESCRIPTION:
XS GIS Cut Line= 3
      2796855.68     10225953.11      2797335.52     10226280.16
      2798305.68     10226353.11
#Sta/Elev= 30
  4419.3    1137  4491.9 1133.57  4534.5 1129.89  4576.6 1127.06  4693.1 1122.19
    4714 1121.88  4758.2 1119.44  4902.5 1114.65  4923.4 1112.55  4944.4 1111.88
  4951.8 1110.99  4993.2 1108.76  4993.5 1108.26    4997 1108.26  4997.2 1108.76
  5020.2    1111  5040.3 1111.49  5070.4  1113.8  5120.5 1114.16  5242.6 1116.73
  5341.1 1120.15  5361.2  1121.5  5411.3 1122.04  5431.4 1123.69  5461.5 1123.56
  5611.9 1128.81  5672.1 1131.93  5682.1 1131.67  5932.8 1141.53  5972.9 1144.36
#Mann= 3 ,-1 , 0
  4419.3     .05       0  4993.2     .03       0  4997.2     .05       0
Bank Sta=4993.2,4997.2
XS Rating Curve= 0 ,0
Exp/Cntr=0.3,0.1

Type RM Length L Ch R = 1 ,17000   ,1000,1000,1000
BEGIN DESCRIPTION:
MARCHISON CREEK 33.0
END DESCRIPTION:
XS GIS Cut Line= 3
       2796605.7     10226203.12        2797107.     10226684.79
      2797905.66      10227053.1
#Sta/Elev= 30
  4304.8 1133.46  4828.2 1113.44  4863.4 1110.82    4899 1111.54  4913.1 1110.19
  4927.3 1105.25  4948.4 1107.53  4955.6 1104.67  4962.5 1105.64  4969.7 1104.22
    5006 1104.62  5009.5 1102.73  5009.8 1102.23  5013.5 1102.73    5029 1105.04
  5034.5 1103.49  5042.6 1105.49  5074.9  1107.4  5080.4 1105.94  5103.3 1108.08
  5195.1 1108.36    5428 1118.59    5510  1120.6  5555.9 1123.92  5722.1 1130.91
  5780.4  1131.7  5796.4 1132.42  5819.4 1135.65  5842.3 1135.78  5879.5 1138.33
#Mann= 3 ,-1 , 0
  4304.8     .05       0  5009.5     .03       0  5013.5     .05       0
Bank Sta=5009.5,5013.5
XS Rating Curve= 0 ,0
Exp/Cntr=0.3,0.1

Type RM Length L Ch R = 1 ,16000   ,500,500,500
BEGIN DESCRIPTION:
MARCHISON CREEK 32.0
END DESCRIPTION:
XS GIS Cut Line= 3
       2796305.7     10226553.13      2797006.19     10227398.65
      2797405.69     10227803.12
#Sta/Elev= 30
    3902 1138.13  4022.4 1134.31  4114.9 1127.79    4292 1119.64  4711.4 1106.93
  4939.4 1104.77  4953.7 1103.61  4960.2 1101.98  4974.5 1101.15  4986.8 1098.73
  4987.1 1098.23  4990.8 1098.73  5003.2  1098.8  5009.8 1100.47  5031.1 1101.23
  5052.3  1103.6  5108.8 1102.32    5116 1101.26    5123  1102.8  5137.1 1103.78
  5158.4 1103.45  5193.7 1105.49  5200.8 1104.68  5243.2 1107.11  5349.3 1110.44
  5476.6 1117.71  5497.8 1118.05  5504.8  1119.4    5512 1118.46  5568.5 1120.94
#Mann= 3 ,-1 , 0
    3902     .05       0  4986.8     .03       0  4990.8     .05       0
Bank Sta=4986.8,4990.8
XS Rating Curve= 0 ,0
Exp/Cntr=0.3,0.1

Type RM Length L Ch R = 1 ,15500   ,315,315,315
BEGIN DESCRIPTION:
MARCHISON CREEK 31.0
END DESCRIPTION:
XS GIS Cut Line= 3
      2795805.69     10227703.11      2796813.47     10227818.79
      2797055.73      10227753.1
#Sta/Elev= 30
  3985.6  1126.4  3997.2 1125.95  4166.8 1117.63  4186.9 1115.81  4398.3  1106.9
  4448.6 1106.01  4519.1 1103.39    4660 1101.83  4670.1 1101.25  4690.2 1097.91
  4710.3 1096.58  4728.2 1100.78  4822.4 1101.24  4841.2 1102.02  4901.5 1100.74
    4962 1098.12    4972  1099.3  4982.1 1099.23  4990.6 1097.28  4993.6 1095.18
  4993.9 1094.68  4997.6 1095.18  4998.6 1096.63    5005 1095.28  5039.7 1099.26
  5044.9  1098.5  5074.3 1100.84  5079.5 1100.25  5085.2 1101.36    5251  1106.6
#Mann= 4 ,-1 , 0
  3985.6     .12       0  3997.2     .05       0  4993.6     .03       0
  4997.6     .05       0
Bank Sta=4993.6,4997.6
XS Rating Curve= 0 ,0
Exp/Cntr=0.3,0.1

Type RM Length L Ch R = 1 ,15185   ,685,685,685
BEGIN DESCRIPTION:
Mapping XS 4c1b4d0c
END DESCRIPTION:
XS GIS Cut Line= 3
      2796024.34     10228239.87      2796903.96     10227978.36
      2797391.02     10228097.15
#Sta/Elev= 30
  4321.1 1109.65  4374.7 1107.68  4447.7 1106.78  4729.4 1099.48  4760.7 1097.21
    4792 1097.52  4810.8 1094.18  4811.1 1093.68  4814.8 1094.18  4818.3 1096.12
  4823.5 1095.47  4833.7 1097.55  4884.7 1099.72    4938 1100.76  4979.8 1099.84
  4994.7 1097.94  5000.6 1094.98    5011 1095.02  5021.5 1097.86  5033.1 1098.82
  5084.1 1098.78  5146.7 1100.25    5178 1098.91  5450.1  1111.5    5467 1113.22
  5533.5 1116.61  5549.3  1118.5  5569.9  1119.1  5658.6 1125.91  5740.1 1129.83
#Mann= 3 ,-1 , 0
  4321.1     .05       0  4810.8     .05       0  4814.8     .05       0
Bank Sta=4810.8,4814.8
XS Rating Curve= 0 ,0
Exp/Cntr=0.3,0.1

Type RM Length L Ch R = 1 ,14500   ,500,500,500
BEGIN DESCRIPTION:
MARCHISON CREEK 29.0
END DESCRIPTION:
XS GIS Cut Line= 3
      2795955.66     10228503.12      2796942.83      10228322.8
      2797205.65     10228253.12
#Sta/Elev= 30
  3996.5 1114.82  4169.3 1107.64  4230.3 1101.84  4251.3 1103.54  4299.5 1100.33
  4304.6 1101.69    4332 1102.78  4352.3  1099.9  4357.8 1099.97  4362.9 1102.03
    4393 1101.79  4443.8 1098.41    4454 1099.84  4565.8 1096.89  4626.8 1092.64
  4667.4 1096.22  4862.4 1097.48    4974  1096.2  4998.9 1092.24  5016.4 1091.24
  5016.6 1090.74  5020.4 1091.24  5023.6 1095.56    5034 1101.47  5053.4 1105.14
  5058.6 1103.53    5065 1105.43  5093.6 1107.81  5189.2  1113.3  5271.9 1122.36
#Mann= 3 ,-1 , 0
  3996.5     .05       0  5016.4     .05       0  5020.4     .05       0
Bank Sta=5016.4,5020.4
XS Rating Curve= 0 ,0
Exp/Cntr=0.3,0.1

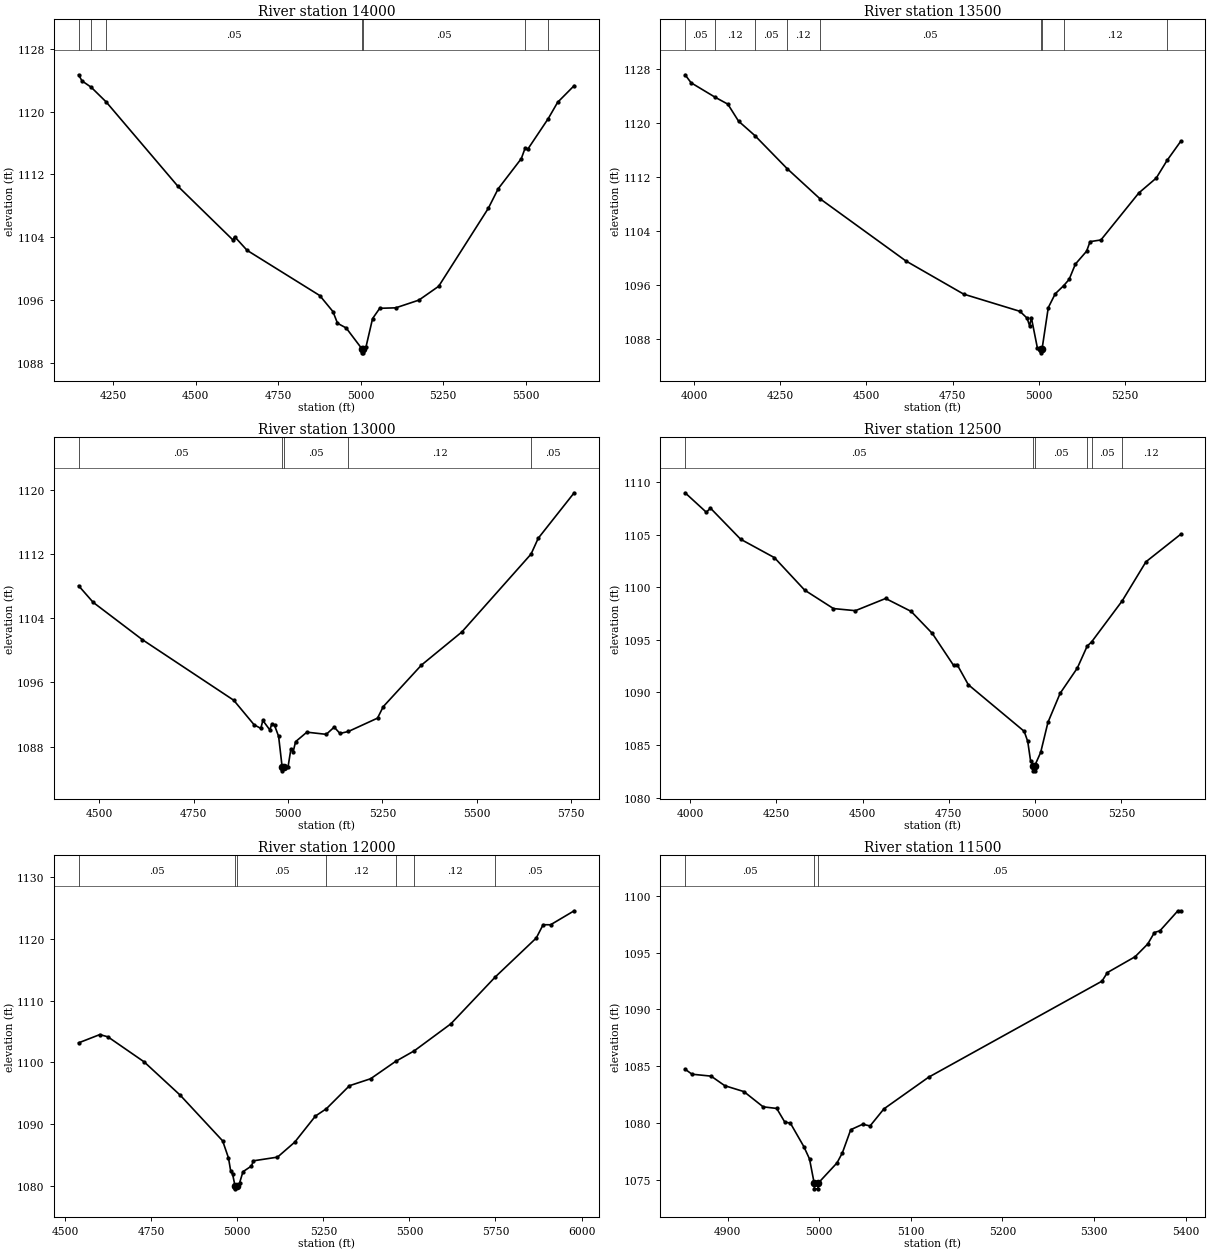
Type RM Length L Ch R = 1 ,14000   ,500,500,500
BEGIN DESCRIPTION:
MARCHISON CREEK 28.0
END DESCRIPTION:
XS GIS Cut Line= 3
       2795755.7     10228603.11      2796609.67     10228575.83
      2797255.69     10228603.11
#Sta/Elev= 30
  4145.6 1124.67  4155.6  1123.9  4183.8 1123.08    4229 1121.22  4445.7 1110.53
  4613.1 1103.67  4618.1  1104.1  4655.8 1102.36    4876 1096.61    4916 1094.57
  4929.7 1093.09    4956 1092.49  5003.9 1089.83  5004.2 1089.33  5007.8 1089.33
  5008.1 1089.83    5016 1090.08    5036 1093.69  5057.6 1094.99  5106.1 1095.05
  5176.2 1096.03  5236.2 1097.79  5386.4 1107.69  5416.4 1110.18  5486.4 1114.01
  5498.1 1115.36  5506.5 1115.24  5567.9 1119.09  5596.5 1121.17  5646.6 1123.29
#Mann= 7 ,-1 , 0
  4145.6     .05       0  4183.8     .12       0    4229     .05       0
  5003.9     .05       0  5008.1     .05       0  5498.1     .12       0
  5567.9     .05       0
Bank Sta=5003.9,5008.1
XS Rating Curve= 0 ,0
Exp/Cntr=0.3,0.1

Type RM Length L Ch R = 1 ,13500   ,500,500,500
BEGIN DESCRIPTION:
MARCHISON CREEK 27.0
END DESCRIPTION:
XS GIS Cut Line= 3
      2795705.73     10228653.12      2796698.43     10228914.36
      2797105.65     10228853.12
#Sta/Elev= 30
  3973.5  1127.1    3991 1125.91  4061.4 1123.75  4097.5 1122.75  4128.6 1120.23
  4175.8  1118.1  4269.5  1113.2  4364.2 1108.76  4614.6  1099.5  4782.1 1094.59
  4945.5 1092.04  4966.1 1091.03  4973.4 1089.89  4978.5 1091.11    4996 1086.62
  5005.2 1086.39  5005.5 1085.89  5009.4 1086.39  5027.6 1092.59  5047.8 1094.64
  5072.6 1095.86  5088.2 1096.78  5106.3 1099.04  5138.8 1100.95  5148.9 1102.37
  5180.4 1102.62  5290.5 1109.59    5341 1111.79  5372.3  1114.4  5411.8 1117.22
#Mann= 9 ,-1 , 0
  3973.5     .05       0  4061.4     .12       0  4175.8     .05       0
  4269.5     .12       0  4364.2     .05       0  5005.2     .05       0
  5009.4     .05       0  5072.6     .12       0  5372.3     .05       0
Bank Sta=5005.2,5009.4
XS Rating Curve= 0 ,0
Exp/Cntr=0.3,0.1

Type RM Length L Ch R = 1 ,13000   ,500,500,500
BEGIN DESCRIPTION:
MARCHISON CREEK 26.0
END DESCRIPTION:
XS GIS Cut Line= 3
      2796005.69     10229153.11      2796518.91     10229365.16
      2797155.72     10228953.09
#Sta/Elev= 30
  4444.7 1108.05  4483.3 1105.98  4613.7 1101.33  4855.9 1093.78    4910 1090.72
  4927.7 1090.27  4933.1 1091.26  4951.6 1090.08    4957 1090.84  4964.1 1090.65
  4974.9 1089.28  4984.2 1085.48  4984.5 1084.98  4988.5 1085.48    5000  1085.5
  5007.5  1087.7  5013.5 1087.37    5020 1088.62  5049.8  1089.8  5101.2 1089.53
  5122.3 1090.43  5137.5 1089.64  5160.1 1089.89  5237.1 1091.55  5252.3 1092.98
  5353.5 1098.16  5460.7 1102.29  5644.2    1112  5663.2 1113.97  5758.5 1119.64
#Mann= 5 ,-1 , 0
  4444.7     .05       0  4984.2     .03       0  4988.5     .05       0
  5160.1     .12       0  5644.2     .05       0
Bank Sta=4984.2,4988.5
XS Rating Curve= 0 ,0
Exp/Cntr=0.3,0.1

Type RM Length L Ch R = 1 ,12500   ,500,500,500
BEGIN DESCRIPTION:
MARCHISON CREEK 25.0
END DESCRIPTION:
XS GIS Cut Line= 3
      2795855.64     10229853.12      2796846.53     10229635.99
       2797105.7     10229303.09
#Sta/Elev= 30
  3985.6 1108.99  4047.1 1107.14  4059.1 1107.53  4146.7 1104.57  4244.6 1102.82
  4332.3 1099.73  4415.6 1097.98  4479.2 1097.78  4566.8 1098.94  4640.8 1097.71
  4702.3 1095.61  4763.7 1092.58  4773.9 1092.66  4806.5 1090.74  4968.4 1086.31
  4978.7 1085.35  4986.9 1083.51  4994.9 1083.05  4995.1 1082.55  4998.9 1082.55
  4999.2 1083.05  5016.3 1084.31  5037.3 1087.16  5072.6 1089.92  5122.4 1092.32
    5151 1094.41  5163.6  1094.8  5252.5 1098.71  5321.4 1102.43  5421.9 1105.04
#Mann= 6 ,-1 , 0
  3985.6     .05       0  4994.9     .03       0  4999.2     .05       0
    5151     .12       0  5163.6     .05       0  5252.5     .12       0
Bank Sta=4994.9,4999.2
XS Rating Curve= 0 ,0
Exp/Cntr=0.3,0.1

Type RM Length L Ch R = 1 ,12000   ,500,500,500
BEGIN DESCRIPTION:
MARCHISON CREEK 24.0
END DESCRIPTION:
XS GIS Cut Line= 3
      2797055.69     10230303.09      2797237.87     10229879.39
      2797305.68     10228903.15
#Sta/Elev= 30
  4538.8 1103.17  4600.4 1104.51  4623.9 1104.14    4729 1100.09    4834 1094.68
  4957.2 1087.28  4974.2 1084.51  4980.7 1082.36  4986.2 1081.87  4993.1    1080
  4993.4  1079.5  4997.5    1080  5006.3 1080.43  5016.3 1082.28    5041  1083.2
  5046.4 1084.04  5116.6 1084.64  5166.7 1087.07  5226.8  1091.3  5258.7 1092.49
  5325.7 1096.22  5387.2 1097.35  5459.5 1100.15  5514.4 1101.89  5620.3 1106.25
  5749.7 1113.87  5868.4 1120.16  5888.4 1122.32    5910 1122.31  5978.6 1124.58
#Mann= 7 ,-1 , 0
  4538.8     .05       0  4993.1     .03       0  4997.5     .05       0
  5258.7     .12       0  5459.5     .05       0  5514.4     .12       0
  5749.7     .05       0
Bank Sta=4993.1,4997.5
XS Rating Curve= 0 ,0
Exp/Cntr=0.3,0.1

Type RM Length L Ch R = 1 ,11500   ,500,500,500
BEGIN DESCRIPTION:
MARCHISON CREEK 23.0
END DESCRIPTION:
XS GIS Cut Line= 3
       2797755.7     10229803.13      2797672.32     10229682.92
      2797455.68      10229353.1
#Sta/Elev= 30
  4853.7 1084.74  4861.2  1084.3  4882.1 1084.13    4897 1083.29  4917.9 1082.77
  4938.9 1081.43  4953.7 1081.29  4962.5 1080.09  4968.6    1080  4983.4 1077.92
  4989.5 1076.85  4994.6 1074.72  4994.9 1074.22  4998.7 1074.22    4999 1074.72
  5019.5  1076.5  5025.4 1077.39  5034.5 1079.42  5047.6  1079.9  5055.6 1079.75
  5070.7 1081.25  5119.4 1084.03  5308.7 1092.48  5314.7 1093.24  5344.9 1094.63
  5358.7 1095.75    5366 1096.76    5372 1096.91  5391.6 1098.67  5394.6 1098.67
#Mann= 3 ,-1 , 0
  4853.7     .05       0  4994.6     .03       0    4999     .05       0
Bank Sta=4994.6,4999
XS Rating Curve= 0 ,0
Exp/Cntr=0.3,0.1

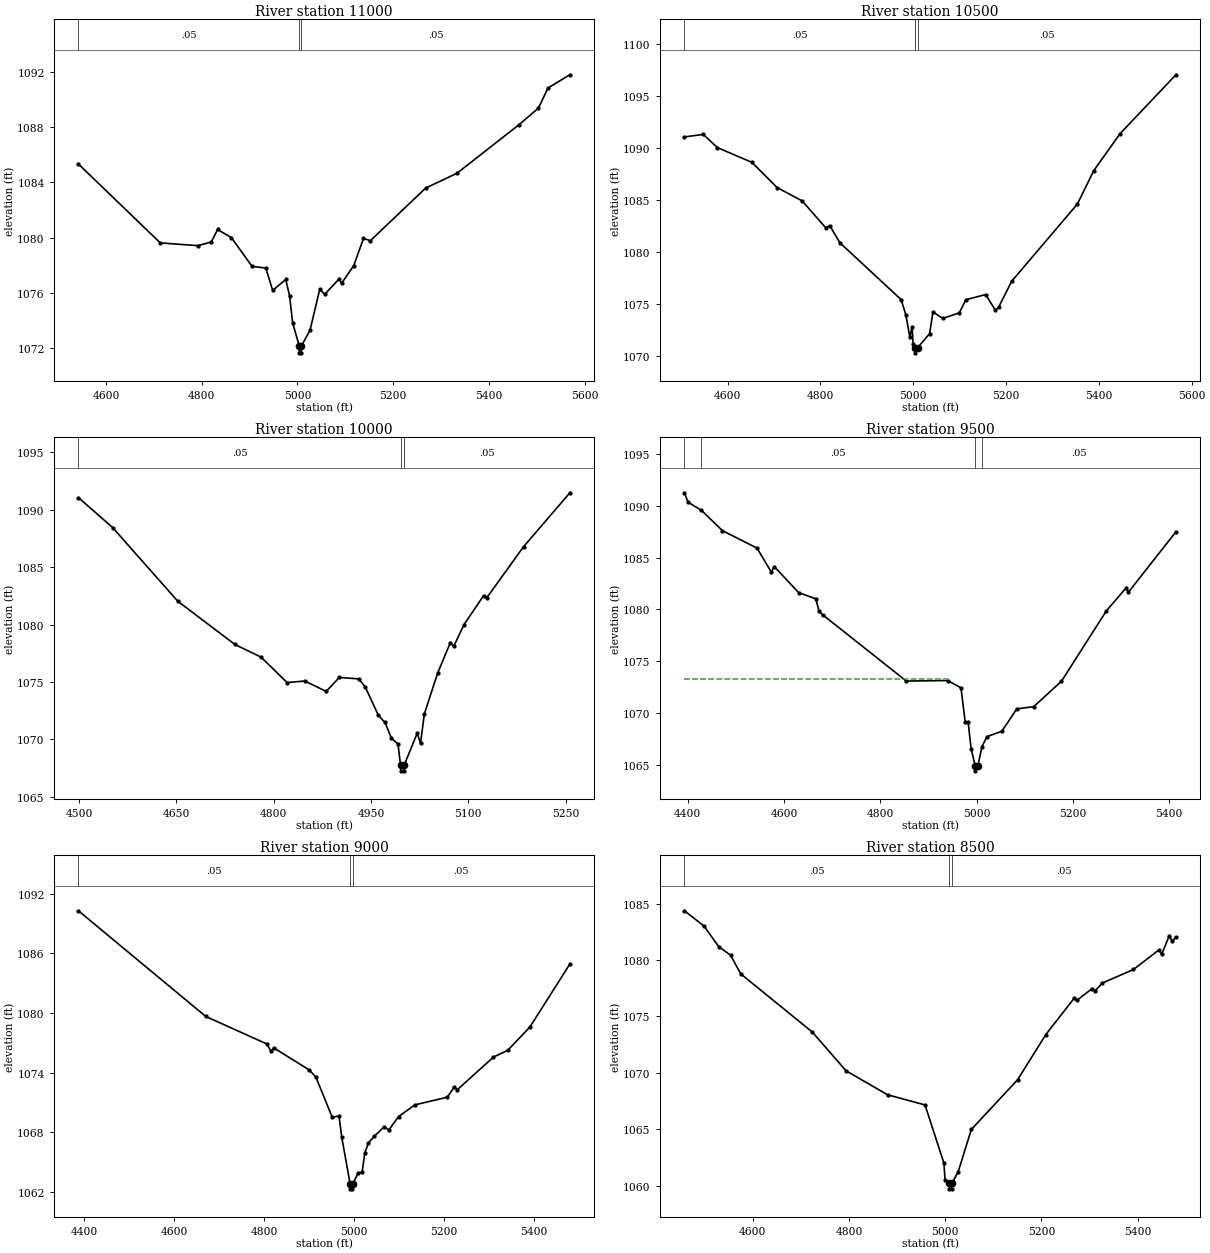
Type RM Length L Ch R = 1 ,11000   ,500,500,500
BEGIN DESCRIPTION:
MARCHISON CREEK 22.0
END DESCRIPTION:
XS GIS Cut Line= 3
      2797780.69     10229828.11      2798135.26     10229539.16
      2798230.68     10228978.12
#Sta/Elev= 30
  4542.6 1085.33  4713.5 1079.62  4791.8 1079.42  4819.9 1079.68  4833.4 1080.59
  4862.1    1080  4905.2 1077.92    4934  1077.8  4948.3 1076.18  4975.6 1076.97
  4983.5 1075.81    4990 1073.83  5003.8 1072.16  5004.1 1071.66  5008.2 1071.66
  5008.5 1072.16  5026.4 1073.31  5046.7 1076.27  5056.9 1075.89  5087.1 1077.01
  5092.2 1076.69  5117.7 1077.98    5138 1079.94  5152.4 1079.78  5267.9 1083.59
  5333.2 1084.66  5462.6 1088.17  5503.2 1089.37  5523.5 1090.84  5569.1 1091.79
#Mann= 3 ,-1 , 0
  4542.6     .05       0  5003.8     .03       0  5008.5     .05       0
Bank Sta=5003.8,5008.5
XS Rating Curve= 0 ,0
Exp/Cntr=0.3,0.1

Type RM Length L Ch R = 1 ,10500   ,500,500,500
BEGIN DESCRIPTION:
MARCHISON CREEK 21.0
END DESCRIPTION:
XS GIS Cut Line= 3
      2797605.68     10230003.11      2798091.28      10229917.4
      2798505.66     10230303.09
#Sta/Elev= 30
  4506.9 1091.08  4547.5 1091.32    4578 1090.05  4652.4 1088.63  4706.6 1086.21
  4760.7 1084.92  4811.5 1082.33    4820 1082.54    4842 1080.89    4974 1075.42
  4984.2 1073.93  4992.6 1071.84  4997.6 1072.77  4999.7 1071.19  5004.1  1070.8
  5004.6  1070.3  5009.7  1070.8  5035.3 1072.15  5042.6 1074.24  5063.6 1073.61
  5099.3 1074.15  5113.5 1075.41    5156 1075.91    5177 1074.41  5183.8 1074.68
  5212.2 1077.19  5353.8 1084.62    5389 1087.83  5445.7 1091.39  5566.1 1097.06
#Mann= 3 ,-1 , 0
  4506.9     .05       0  5004.1     .03       0  5009.7     .05       0
Bank Sta=5004.1,5009.7
XS Rating Curve= 0 ,0
Exp/Cntr=0.3,0.1

Type RM Length L Ch R = 1 ,10000   ,500,500,500
BEGIN DESCRIPTION:
MARCHISON CREEK 20.0
END DESCRIPTION:
XS GIS Cut Line= 3
      2797605.66     10230353.11      2798103.96     10230403.08
      2798355.65     10230353.12
#Sta/Elev= 30
  4499.2 1091.07  4551.9 1088.46  4652.3 1082.04  4740.4 1078.27  4780.6 1077.17
  4820.8 1074.95    4848 1075.09  4881.1 1074.18  4901.2  1075.4  4931.4 1075.27
  4941.4 1074.54  4961.5 1072.09  4971.6 1071.48  4981.6 1070.11  4991.7 1069.59
  4995.6 1067.76    4996 1067.26  5000.7 1067.26  5001.2 1067.76  5021.3 1070.54
  5026.4 1069.66  5032.3 1072.22  5052.7 1075.76  5072.4 1078.44  5077.5  1078.1
  5093.5 1080.01  5123.6 1082.53  5128.7 1082.36  5185.3  1086.8  5256.6 1091.49
#Mann= 3 ,-1 , 0
  4499.2     .05       0  4995.6     .05       0  5001.2     .05       0
Bank Sta=4995.6,5001.2
XS Rating Curve= 0 ,0
Exp/Cntr=0.3,0.1

Type RM Length L Ch R = 1 ,9500    ,500,500,500
BEGIN DESCRIPTION:
MARCHISON CREEK 19.0
END DESCRIPTION:
XS GIS Cut Line= 3
      2797555.65     10230553.09      2798054.99     10230898.21
      2798455.68     10231003.11
#Sta/Elev= 30
    4393 1091.25  4400.5 1090.34  4428.4 1089.55  4472.1 1087.59  4543.8 1085.91
  4573.5 1083.59  4579.6 1084.13  4630.3 1081.61  4666.1 1081.01  4672.6 1079.82
    4681 1079.44    4854 1073.07  4940.1 1073.12  4967.6 1072.42  4976.4 1069.11
  4982.4 1069.14  4988.7 1066.54  4997.1  1064.9  4997.5  1064.4  5002.8  1064.9
  5011.1 1066.72  5021.4  1067.7  5052.4 1068.22  5083.6 1070.38  5118.8  1070.6
  5176.4 1073.05  5269.5 1079.83  5310.6 1082.06  5315.7 1081.66  5414.2 1087.48
#Mann= 4 ,-1 , 0
    4393     .12       0  4428.4     .05       0  4997.1     .05       0
  5011.1     .05       0
#XS Ineff= 2 , 0
         4940.57 1073.26
Permanent Ineff=
       F       F
Bank Sta=4997.1,5002.8
XS Rating Curve= 0 ,0
Exp/Cntr=0.3,0.1

Type RM Length L Ch R = 1 ,9000    ,500,500,500
BEGIN DESCRIPTION:
MARCHISON CREEK 18.0
END DESCRIPTION:
XS GIS Cut Line= 3
      2797555.69     10230703.11      2797887.56     10231217.67
      2798305.72     10231453.13
#Sta/Elev= 30
  4387.7  1090.3  4670.5 1079.66  4806.5 1076.88  4815.7 1076.15  4821.6 1076.49
  4900.2 1074.28  4915.4 1073.55  4951.7  1069.5  4966.8 1069.63  4972.8  1067.5
  4991.5 1062.79  4991.9 1062.29  4996.7 1062.29  4997.2 1062.79  5009.3 1063.87
  5018.2 1063.96  5023.9 1065.87  5032.3 1066.94  5045.6 1067.59  5067.2 1068.55
  5077.4 1068.21  5099.1 1069.57  5135.6 1070.75  5207.4 1071.52  5223.4 1072.57
  5229.1 1072.25    5310 1075.56  5341.9 1076.25    5391 1078.59  5479.9 1084.94
#Mann= 3 ,-1 , 0
  4387.7     .05       0  4991.5     .05       0  4997.2     .05       0
Bank Sta=4991.5,4997.2
XS Rating Curve= 0 ,0
Exp/Cntr=0.3,0.1

Type RM Length L Ch R = 1 ,8500    ,500,500,500
BEGIN DESCRIPTION:
MARCHISON CREEK 17.0
END DESCRIPTION:
XS GIS Cut Line= 3
      2797305.68     10231003.09      2797490.97     10231512.54
      2797905.65     10231753.09
#Sta/Elev= 30
  4457.9 1084.36  4498.5 1083.01  4529.1 1081.19  4553.7 1080.43    4575 1078.77
  4723.9 1073.61  4793.7 1070.19  4880.2 1068.06    4958 1067.16  4997.2 1062.01
  4999.6 1060.51  5008.3 1060.23  5008.8 1059.73  5013.6 1059.73  5014.1 1060.23
  5026.9 1061.25  5054.2 1064.99  5150.3 1069.39  5209.1  1073.4  5267.9 1076.61
  5273.7 1076.43  5305.1 1077.46  5310.9 1077.25  5326.7 1077.96  5391.2 1079.16
  5444.3  1080.9    5450 1080.52  5465.8 1082.17  5471.6 1081.65  5479.4 1082.03
#Mann= 3 ,-1 , 0
  4457.9     .05       0  5008.3     .05       0  5014.1     .05       0
Bank Sta=5008.3,5014.1
XS Rating Curve= 0 ,0
Exp/Cntr=0.3,0.1