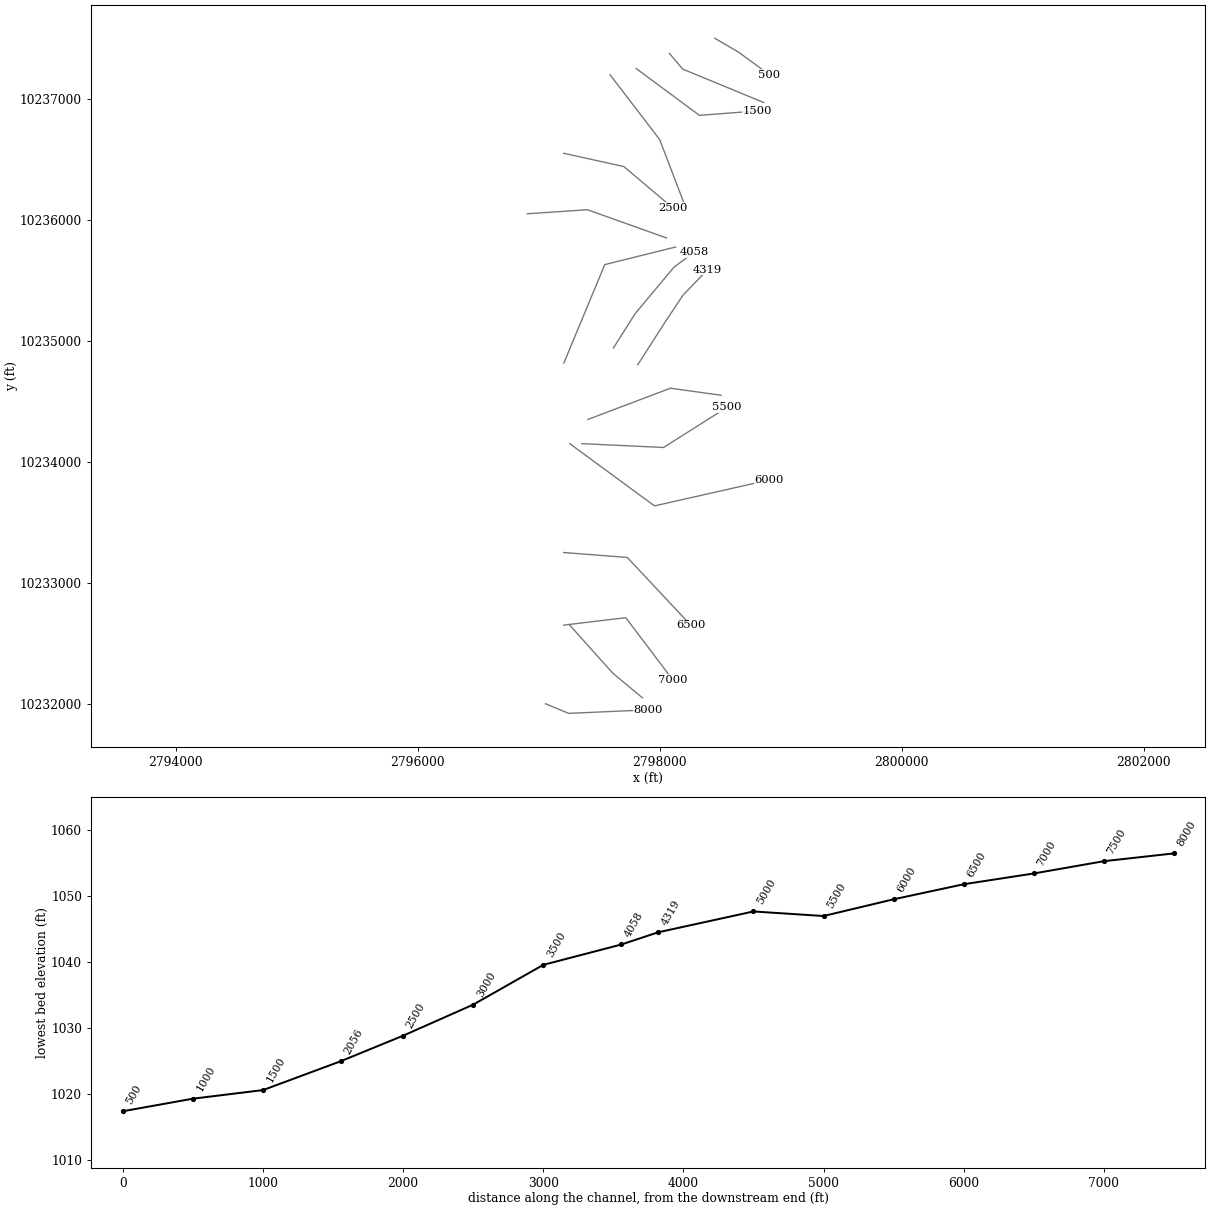
HEC-RAS study MARCHISON CREEK.prj: MARCHISON CREEK Base Level Engineering

--- MARCHISON CREEK.g01 (geometry) --- (continued)

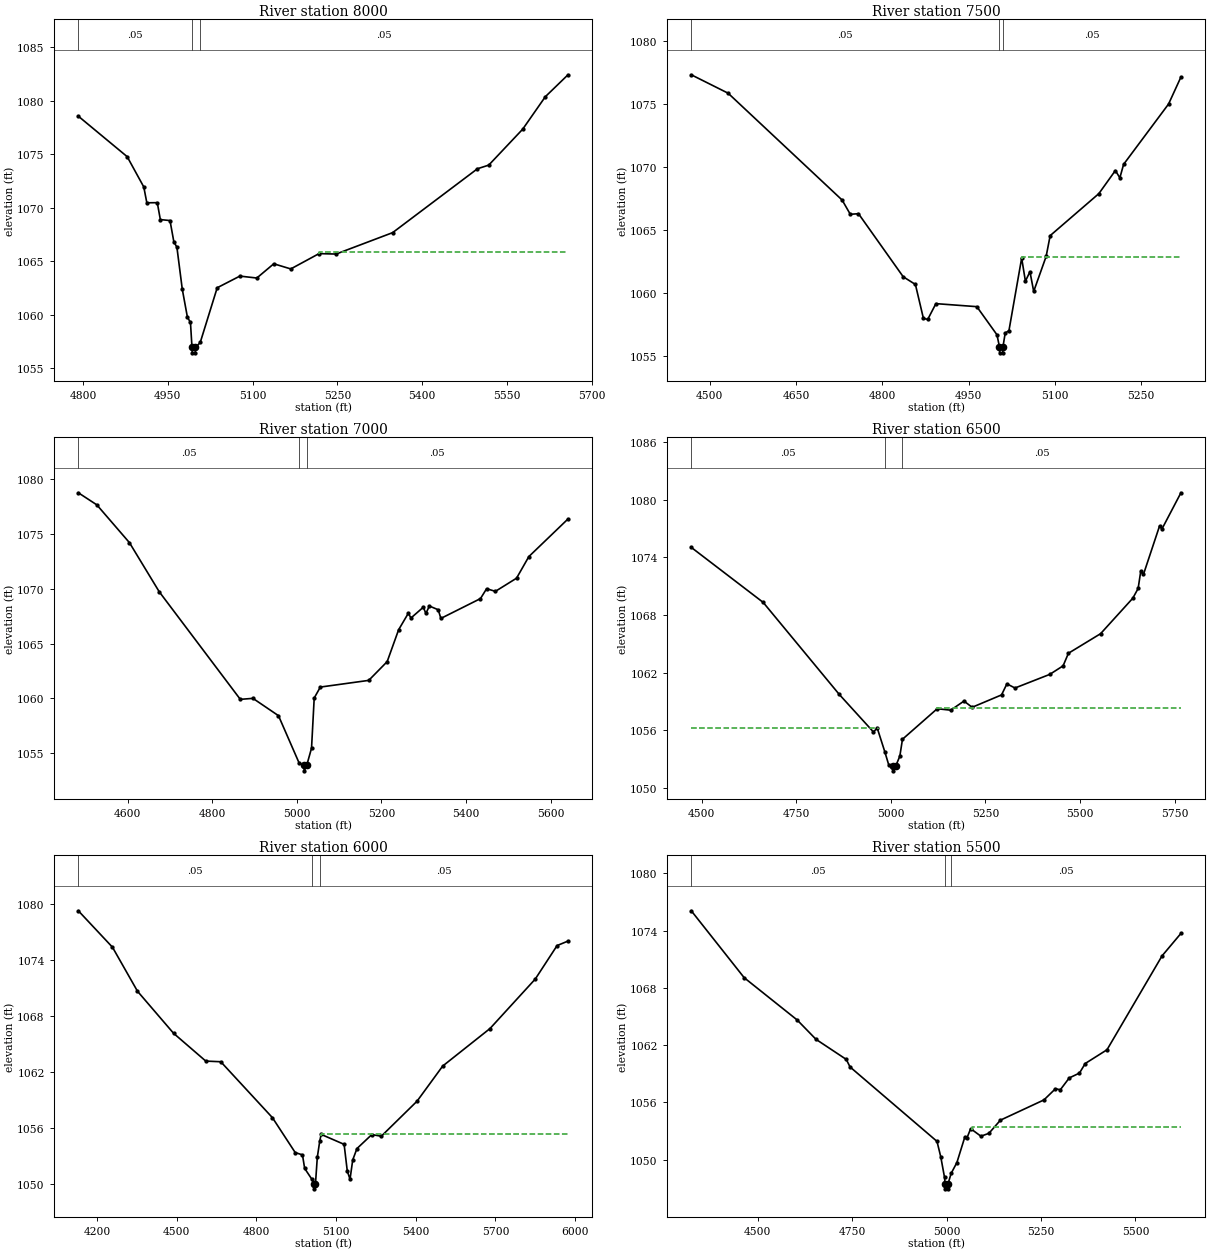
Type RM Length L Ch R = 1 ,8000    ,500,500,500
BEGIN DESCRIPTION:
MARCHISON CREEK 16.0
END DESCRIPTION:
XS GIS Cut Line= 3
      2797055.72      10232003.1      2797248.28     10231923.67
      2797905.72     10231953.11
#Sta/Elev= 30
  4791.7 1078.55  4878.1 1074.77  4907.5 1071.94  4912.9 1070.46  4931.4 1070.47
  4936.8 1068.89  4953.9  1068.8  4960.7 1066.81  4966.1 1066.31  4975.6 1062.39
  4984.7 1059.77  4990.1 1059.28  4992.8 1056.94  4993.3 1056.44  4998.5 1056.44
    4999 1056.94  5007.4 1057.41  5037.4 1062.52  5077.5 1063.61  5107.5 1063.43
  5137.5 1064.76  5167.6 1064.28  5217.6 1065.71  5247.7 1065.67  5347.8 1067.67
  5497.9 1073.64  5517.9 1073.98    5578 1077.34    5618 1080.37  5658.1 1082.42
#Mann= 3 ,-1 , 0
  4791.7     .05       0  4992.8     .05       0  5007.4     .05       0
#XS Ineff= 2 , 0
                         5218.41         1065.84
Permanent Ineff=
       F       F
Bank Sta=4992.8,4999
XS Rating Curve= 0 ,0
Exp/Cntr=0.3,0.1

Type RM Length L Ch R = 1 ,7500    ,500,500,500
BEGIN DESCRIPTION:
MARCHISON CREEK 15.0
END DESCRIPTION:
XS GIS Cut Line= 3
      2797255.67     10232653.13      2797610.55     10232257.07
      2797855.69      10232053.1
#Sta/Elev= 30
  4468.2  1077.3  4532.2 1075.84  4730.3 1067.37  4744.5 1066.24  4758.7 1066.29
  4836.4 1061.29  4857.6 1060.68  4871.5 1057.99    4879 1057.91  4893.2 1059.16
  4964.3 1058.92  4999.3 1056.69  5003.5 1055.76    5004 1055.26  5009.3 1055.26
  5009.8 1055.76  5013.6 1056.83  5020.1 1057.02  5042.2 1062.77  5048.7 1060.94
  5056.6 1061.69  5063.1 1060.13  5084.7  1062.9  5091.7 1064.55  5176.3 1067.88
    5205 1069.71  5212.8 1069.13  5219.3  1070.2  5297.4 1074.98  5318.9 1077.12
#Mann= 3 ,-1 , 0
  4468.2     .05       0  5003.5     .05       0  5009.8     .05       0
#XS Ineff= 2 , 0
                         5042.05         1062.84
Permanent Ineff=
       F       F
Bank Sta=5003.5,5009.8
XS Rating Curve= 0 ,0
Exp/Cntr=0.3,0.1

Type RM Length L Ch R = 1 ,7000    ,500,500,500
BEGIN DESCRIPTION:
MARCHISON CREEK 14.0
END DESCRIPTION:
XS GIS Cut Line= 3
      2797205.65     10232653.11      2797718.98     10232714.59
      2798105.68     10232203.12
#Sta/Elev= 30
    4483 1078.76  4526.7 1077.66  4603.9 1074.21  4674.4 1069.73  4866.1 1059.92
    4896 1060.01  4956.4 1058.43  5005.5 1054.09  5016.8  1053.9  5017.3  1053.4
  5023.2  1053.9  5034.6 1055.47  5040.9 1060.04  5055.4 1061.04  5169.9 1061.65
  5213.5 1063.36  5240.6 1066.27  5263.5 1067.77  5269.8 1067.34  5298.9 1068.32
  5305.1 1067.76  5313.4 1068.43  5334.3 1068.09  5340.5  1067.3  5434.2 1069.11
  5448.7 1070.01  5469.5 1069.77  5519.5 1070.97  5548.6 1072.94  5641.2 1076.37
#Mann= 3 ,-1 , 0
    4483     .05       0  5005.5     .05       0  5023.2     .05       0
Bank Sta=5016.8,5023.2
XS Rating Curve= 0 ,0
Exp/Cntr=0.3,0.1

Type RM Length L Ch R = 1 ,6500    ,500,500,500
BEGIN DESCRIPTION:
MARCHISON CREEK 13.0
END DESCRIPTION:
XS GIS Cut Line= 3
      2797205.73     10233253.11      2797731.66     10233212.44
      2798255.71     10232653.08
#Sta/Elev= 30
  4472.5 1075.05  4662.5 1069.32  4863.6 1059.73  4953.9 1055.82  4963.9 1056.23
    4984 1053.75    4994 1052.43  5006.3 1052.27  5006.8 1051.77  5012.8 1052.27
  5023.7 1053.31  5030.6 1055.06  5122.4 1058.24  5158.1 1058.09  5193.2 1059.04
  5214.7 1058.39  5292.4 1059.68  5306.6 1060.83    5328  1060.4  5419.9 1061.82
  5455.1 1062.71  5469.2 1064.02  5554.2 1066.06  5639.2 1069.75  5653.4 1070.77
  5660.2 1072.54  5667.5 1072.24    5710 1077.28  5716.9 1077.01  5766.5 1080.74
#Mann= 3 ,-1 , 0
  4472.5     .05       0    4984     .05       0  5030.6     .05       0
#XS Ineff= 2 , 0
         4964.77 1056.26 5121.48         1058.36
Permanent Ineff=
       F       F
Bank Sta=5006.3,5012.8
XS Rating Curve= 0 ,0
Exp/Cntr=0.3,0.1

Type RM Length L Ch R = 1 ,6000    ,500,500,500
BEGIN DESCRIPTION:
MARCHISON CREEK 12.0
END DESCRIPTION:
XS GIS Cut Line= 3
      2797255.71     10234153.09      2797956.77     10233638.58
      2798905.72     10233853.12
#Sta/Elev= 30
  4130.4 1079.31  4258.9  1075.4    4353 1070.68  4488.8 1066.17    4610 1063.19
  4666.4 1063.12  4860.8 1057.12  4946.5 1053.38  4973.8 1053.13    4982 1051.68
  5009.1 1050.52  5016.1 1049.99  5016.6 1049.49  5022.6 1049.99  5029.6 1052.87
    5039 1054.65  5044.1 1055.33  5130.5 1054.26  5142.4  1051.4  5152.7 1050.52
  5162.9 1052.59  5178.8 1053.81  5234.7 1055.31  5270.3 1055.13  5404.9 1058.89
  5501.5 1062.66  5679.4 1066.68  5849.8 1071.99  5931.9 1075.58  5972.9 1076.06
#Mann= 3 ,-1 , 0
  4130.4     .05       0  5009.1     .05       0    5039     .05       0
#XS Ineff= 2 , 0
                         5043.18         1055.37
Permanent Ineff=
       F       F
Bank Sta=5016.1,5022.6
XS Rating Curve= 0 ,0
Exp/Cntr=0.3,0.1

Type RM Length L Ch R = 1 ,5500    ,500,500,500
BEGIN DESCRIPTION:
MARCHISON CREEK 11.0
END DESCRIPTION:
XS GIS Cut Line= 3
      2797355.64     10234153.11       2798031.2     10234121.35
      2798555.68     10234453.11
#Sta/Elev= 30
  4323.7 1076.07  4463.9 1069.06  4604.1 1064.64  4654.1 1062.61  4734.2 1060.51
  4744.2 1059.72  4974.5 1051.93  4984.5 1050.31  4994.5 1048.15  4995.9 1047.46
  4996.4 1046.96  5003.1 1046.96  5003.6 1047.46  5011.9 1048.57  5027.2 1049.71
  5048.4 1052.41  5054.3 1052.33  5063.7 1053.26  5090.8 1052.47    5112 1052.77
  5142.5 1054.15  5257.8 1056.27  5288.3 1057.44  5301.1 1057.33  5324.8 1058.57
  5351.9 1059.08  5367.1 1060.08  5424.8 1061.52  5570.6 1071.35  5620.6  1073.7
#Mann= 3 ,-1 , 0
  4323.7     .05       0  4995.9     .05       0  5011.9     .05       0
#XS Ineff= 2 , 0
                         5068.18          1053.4
Permanent Ineff=
       F       F
Bank Sta=4995.9,5003.6
XS Rating Curve= 0 ,0
Exp/Cntr=0.3,0.1

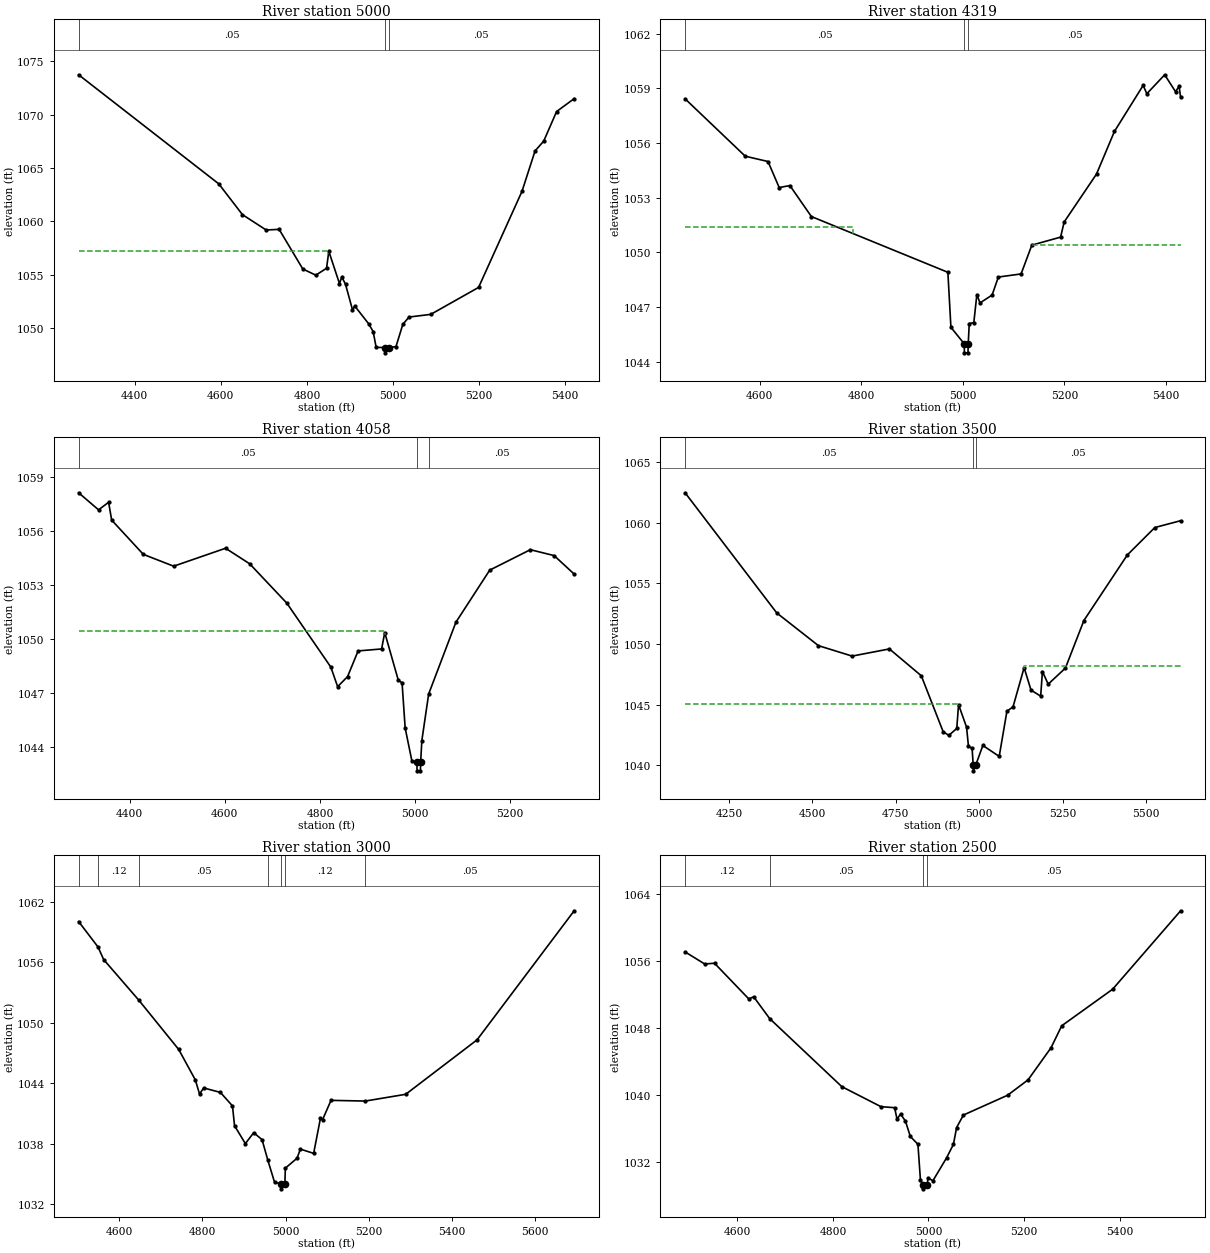
Type RM Length L Ch R = 1 ,5000    ,681,681,681
BEGIN DESCRIPTION:
MARCHISON CREEK 10.0
END DESCRIPTION:
XS GIS Cut Line= 3
      2797405.71     10234353.12      2798088.94     10234611.36
      2798505.69     10234553.11
#Sta/Elev= 30
  4269.6 1073.75  4595.2 1063.51  4650.2 1060.62  4705.3 1059.18  4735.4 1059.24
  4790.4 1055.52  4820.6 1054.94  4845.5 1055.59  4850.8 1057.18  4875.6 1054.15
    4881 1054.77  4889.6 1054.09  4905.8 1051.69  4911.2 1052.04  4943.1 1050.39
  4953.8 1049.65  4960.8 1048.16  4981.8 1048.15  4982.3 1047.65  4989.6 1048.15
  5006.8 1048.23  5022.7 1050.32  5037.1 1051.01  5087.6 1051.26  5198.7 1053.79
  5299.6 1062.81  5329.9  1066.6  5350.1 1067.53    5380  1070.3  5420.8 1071.51
#Mann= 3 ,-1 , 0
  4269.6     .05       0  4981.8     .05       0  4989.6     .05       0
#XS Ineff= 2 , 0
         4849.89 1057.22
Permanent Ineff=
       F       F
Bank Sta=4981.8,4989.6
XS Rating Curve= 0 ,0
Exp/Cntr=0.3,0.1

Type RM Length L Ch R = 1 ,4319    ,261,261,261
BEGIN DESCRIPTION:
Mapping XS 6cd68af1
END DESCRIPTION:
XS GIS Cut Line= 4
      2797818.54     10234805.61      2798040.75     10235152.81
      2798193.53     10235381.98      2798393.87     10235589.23
#Sta/Elev= 30
    4453 1058.43  4571.5 1055.28  4616.3 1054.99  4638.3 1053.56  4659.4 1053.67
  4701.7 1051.97  4970.5 1048.91  4976.5 1045.89  5002.6 1044.99  5003.1 1044.49
  5010.1 1044.49  5010.6 1044.99  5012.6  1046.1  5021.6 1046.15  5027.6 1047.69
  5033.8 1047.23  5057.6 1047.66  5069.9 1048.65  5114.7 1048.82  5135.8  1050.4
  5192.5 1050.84  5199.5 1051.67  5263.2  1054.3  5298.5 1056.64  5355.1 1059.17
  5362.3 1058.71  5397.5 1059.75  5418.9 1058.82  5425.8 1059.12  5428.9 1058.51
#Mann= 3 ,-1 , 0
    4453     .05       0  5002.6     .05       0  5010.6     .05       0
#XS Ineff= 2 , 0
         4783.86 1051.42 5136.36         1050.42
Permanent Ineff=
       F       F
Bank Sta=5002.6,5010.6
XS Rating Curve= 0 ,0
Exp/Cntr=0.3,0.1

Type RM Length L Ch R = 1 ,4058    ,558,558,558
BEGIN DESCRIPTION:
Mapping XS 85efd79f
END DESCRIPTION:
XS GIS Cut Line= 4
      2797617.15      10234944.5       2797797.7      10235229.2
      2798117.14     10235611.15      2798282.22     10235734.96
#Sta/Elev= 30
    4293 1058.14  4334.9 1057.19    4356 1057.61  4362.4 1056.62  4428.9 1054.71
  4492.7 1054.05  4601.8 1055.05  4652.6 1054.18  4730.6 1051.99    4823 1048.43
  4837.3 1047.34  4858.2  1047.9  4880.3 1049.33  4929.7 1049.44  4936.3 1050.35
  4964.9 1047.69  4972.7 1047.56  4979.2 1045.04  4993.5 1043.18  5003.8 1043.15
  5004.3 1042.65  5011.3 1042.65  5011.8 1043.15  5014.3 1044.34  5028.6 1046.93
  5085.9 1050.93  5156.9 1053.83  5242.3 1054.97  5292.3 1054.64  5334.4 1053.61
#Mann= 3 ,-1 , 0
    4293     .05       0  5003.8     .05       0  5028.6     .05       0
#XS Ineff= 2 , 0
         4937.73 1050.42
Permanent Ineff=
       F       F
Bank Sta=5003.8,5011.8
XS Rating Curve= 0 ,0
Exp/Cntr=0.3,0.1

Type RM Length L Ch R = 1 ,3500    ,500,500,500
BEGIN DESCRIPTION:
MARCHISON CREEK 7.0
END DESCRIPTION:
XS GIS Cut Line= 3
      2797207.43      10234819.5      2797545.52     10235633.15
      2798130.64      10235778.1
#Sta/Elev= 30
  4118.9 1062.46  4393.5 1052.56  4518.2 1049.87    4619 1049.01  4730.7  1049.6
  4826.2 1047.39  4891.7 1042.78  4908.6 1042.48  4932.4 1043.05  4937.8 1045.01
  4961.7 1043.16  4967.5 1041.57  4978.3 1041.42  4981.6 1040.06  4982.1 1039.56
  4989.6 1040.06  5010.5 1041.65  5059.5 1040.75  5082.6 1044.47  5100.9 1044.83
  5134.1 1048.06  5154.7 1046.21  5183.7 1045.71  5188.9 1047.74  5206.2  1046.7
  5257.7 1048.02  5313.1 1051.94  5443.2 1057.34  5525.6  1059.6  5602.8 1060.16
#Mann= 3 ,-1 , 0
  4118.9     .05       0  4981.6     .05       0  4989.6     .05       0
#XS Ineff= 2 , 0
         4938.86 1045.09 5133.18         1048.16
Permanent Ineff=
       F       F
Bank Sta=4981.6,4989.6
XS Rating Curve= 0 ,0
Exp/Cntr=0.3,0.1

Type RM Length L Ch R = 1 ,3000    ,500,500,500
BEGIN DESCRIPTION:
MARCHISON CREEK 6.0
END DESCRIPTION:
XS GIS Cut Line= 3
      2796905.66     10236053.11      2797402.35     10236086.39
      2798055.65     10235853.12
#Sta/Elev= 30
  4502.2 1060.06  4548.8 1057.54  4562.4 1056.29  4647.5 1052.23  4742.8 1047.37
  4782.8 1044.35  4792.9 1042.95  4802.9 1043.55    4843 1043.11  4872.1 1041.77
  4877.1  1039.8  4903.1 1038.03  4923.2 1039.11  4943.2 1038.42  4957.3 1036.36
  4973.3 1034.19  4988.5 1034.04    4989 1033.54  4998.1 1034.04  4999.2 1035.59
  5027.4 1036.58  5035.4 1037.48  5067.3 1037.06  5083.6 1040.54  5088.9 1040.42
  5109.1 1042.32  5191.4 1042.25  5288.6 1042.92  5460.1 1048.32  5693.7 1061.13
#Mann= 7 ,-1 , 0
  4502.2     .05       0  4548.8     .12       0  4647.5     .05       0
  4957.3     .12       0  4988.5     .07       0  4998.1     .12       0
  5191.4     .05       0
Bank Sta=4988.5,4998.1
XS Rating Curve= 0 ,0
Exp/Cntr=0.3,0.1

Type RM Length L Ch R = 1 ,2500    ,444,444,444
BEGIN DESCRIPTION:
MARCHISON CREEK 5.0
END DESCRIPTION:
XS GIS Cut Line= 3
      2797205.65     10236553.12       2797702.8     10236443.49
      2798105.67     10236103.13
#Sta/Elev= 30
  4490.9 1057.07  4531.9 1055.63  4552.4 1055.72  4624.1 1051.47  4634.3 1051.72
  4667.9 1049.12  4818.6 1041.02  4900.6 1038.63  4929.1 1038.51  4934.2 1037.14
  4941.5 1037.76  4951.8 1036.91    4962 1035.08  4977.9 1034.15  4983.1 1029.93
  4987.9 1029.34  4988.4 1028.84  4997.5 1029.34  4998.9 1030.14  5009.3 1029.81
  5037.9 1032.54  5052.2 1034.15  5058.8 1036.14    5073 1037.63  5165.4 1039.99
  5208.2 1041.82  5256.3 1045.65  5278.7 1048.27  5385.1 1052.62  5527.4 1061.97
#Mann= 4 ,-1 , 0
  4490.9     .12       0  4667.9     .05       0  4987.9     .05       0
  4997.5     .05       0
Bank Sta=4987.9,4997.5
XS Rating Curve= 0 ,0
Exp/Cntr=0.3,0.1

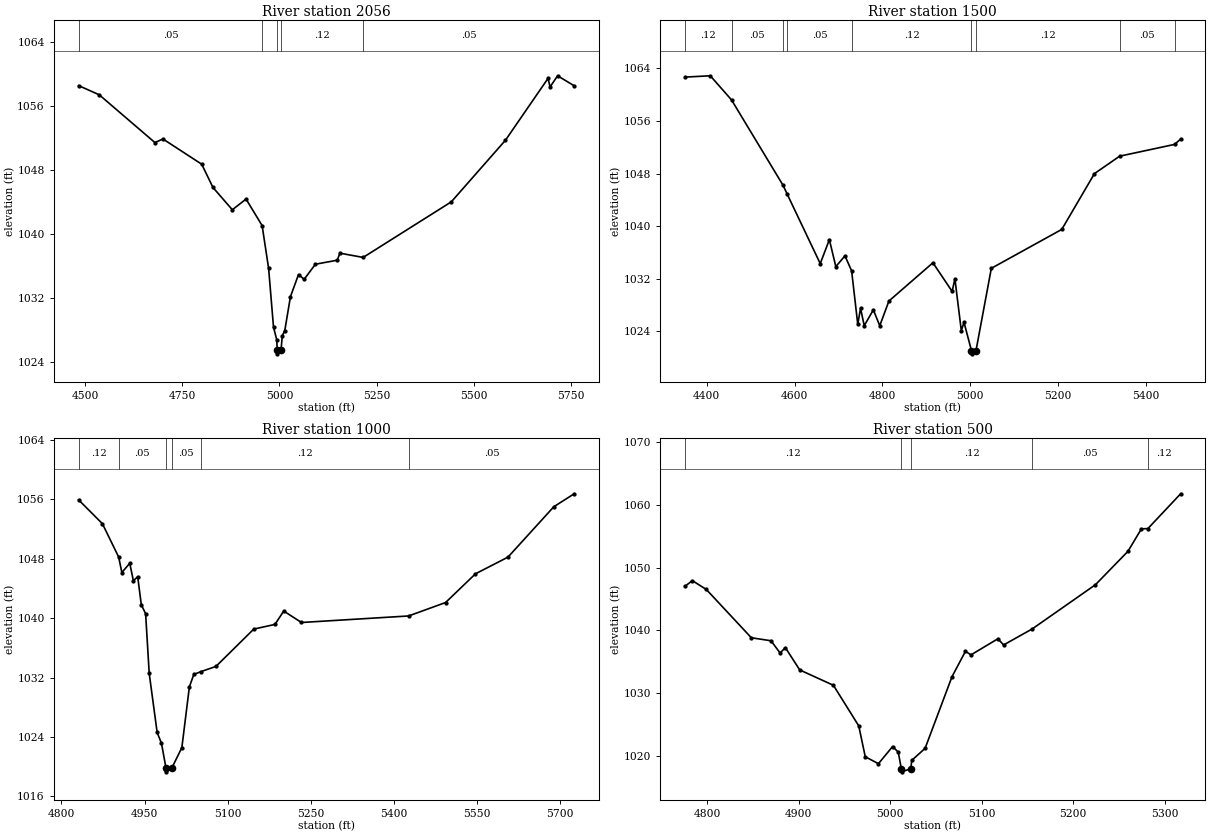
Type RM Length L Ch R = 1 ,2056    ,556,556,556
BEGIN DESCRIPTION:
Mapping XS 93fbd9c8
END DESCRIPTION:
XS GIS Cut Line= 3
      2797589.34     10237201.45      2797999.09      10236666.7
      2798214.38     10236104.17
#Sta/Elev= 30
  4482.8 1058.53  4535.9 1057.38  4679.1 1051.41    4700 1051.85  4799.7  1048.7
  4828.7 1045.79  4878.6    1043  4913.9 1044.34  4955.3 1041.02    4972 1035.67
  4984.6 1028.32  4992.8 1026.76  4994.3 1025.48  4994.8 1024.98    5004 1025.48
  5007.3 1027.27  5013.6 1027.88  5028.2 1032.13    5049  1034.9  5063.5  1034.3
  5092.5 1036.19  5148.7 1036.69  5155.6 1037.57  5215.4 1037.04  5442.4 1043.99
  5581.9  1051.7  5691.4 1059.43  5696.8 1058.37  5716.1 1059.76  5758.8 1058.51
#Mann= 5 ,-1 , 0
  4482.8     .05       0  4955.3     .12       0  4994.3     .07       0
    5004     .12       0  5215.4     .05       0
Bank Sta=4994.3,5004
XS Rating Curve= 0 ,0
Exp/Cntr=0.3,0.1

Type RM Length L Ch R = 1 ,1500    ,500,500,500
BEGIN DESCRIPTION:
MARCHISON CREEK 3.0
END DESCRIPTION:
XS GIS Cut Line= 3
      2797805.66     10237253.13      2798327.51     10236866.62
      2798805.72     10236903.11
#Sta/Elev= 30
  4350.6 1062.66    4408 1062.86  4456.4 1059.19    4574 1046.19  4583.3 1044.86
  4658.5 1034.31  4679.3 1037.96    4694 1033.85  4714.8  1035.5    4730 1033.21
    4744 1025.08  4750.3 1027.52  4758.7 1024.88  4779.5 1027.28  4794.1 1024.87
    4815 1028.63  4915.2 1034.44    4959 1030.09  4965.3 1032.01  4979.9 1024.13
  4986.1 1025.37    5003  1021.1  5003.5  1020.6  5013.4  1021.1  5048.3  1033.6
  5208.8 1039.51  5283.2 1047.99  5340.6 1050.64  5465.8 1052.43  5479.6 1053.24
#Mann= 9 ,-1 , 0
  4350.6     .12       0  4456.4     .05       0    4574     .12       0
  4583.3     .05       0    4730     .12       0    5003     .07       0
  5013.4     .12       0  5340.6     .05       0  5465.8     .12       0
Bank Sta=5003,5013.4
XS Rating Curve= 0 ,0
Exp/Cntr=0.3,0.1

Type RM Length L Ch R = 1 ,1000    ,500,500,500
BEGIN DESCRIPTION:
MARCHISON CREEK 2.0
END DESCRIPTION:
XS GIS Cut Line= 3
      2798080.71     10237378.08      2798189.59     10237248.96
      2798860.24     10236972.24
#Sta/Elev= 30
  4831.1 1055.94    4874 1052.73  4903.4 1048.23  4909.1 1046.15  4923.4  1047.4
  4929.9 1045.04  4937.7 1045.59  4944.2 1041.82    4952  1040.6  4958.5 1032.55
  4972.8 1024.61  4980.6 1023.15  4988.8  1019.8  4989.3  1019.3  4999.2  1019.8
  5017.4 1022.56    5031 1030.75    5039 1032.42  5051.7  1032.8  5078.9  1033.5
  5147.2 1038.53  5185.4 1039.16  5201.3 1040.96  5233.3 1039.42  5426.7  1040.3
  5493.4 1042.11  5547.4 1045.98  5606.1 1048.23  5688.7 1055.01  5725.5 1056.76
#Mann= 6 ,-1 , 0
  4831.1     .12       0  4903.4     .05       0  4988.8     .05       0
  4999.2     .05       0  5051.7     .12       0  5426.7     .05       0
Bank Sta=4988.8,4999.2
XS Rating Curve= 0 ,0
Exp/Cntr=0.3,0.1

Type RM Length L Ch R = 1 ,500     ,0,0,0
BEGIN DESCRIPTION:
MARCHISON CREEK 1.0
END DESCRIPTION:
XS GIS Cut Line= 3
      2798455.64     10237503.14      2798649.22     10237390.23
      2798905.71     10237203.09
#Sta/Elev= 30
  4775.9 1047.04  4783.8 1047.93  4799.1 1046.52  4848.3 1038.81  4869.8 1038.33
  4879.7 1036.38  4885.5 1037.23  4901.2 1033.67    4938 1031.22  4965.7 1024.74
  4972.8 1019.81  4987.2  1018.7  5002.7 1021.44  5008.9 1020.54  5012.2  1017.9
  5012.7  1017.4  5022.6  1017.9  5023.6 1019.23  5038.2 1021.15  5067.6 1032.59
  5082.3 1036.64  5088.4 1036.08  5117.8 1038.65    5124 1037.66  5155.4 1040.23
  5224.4 1047.28  5259.9 1052.61  5274.6  1056.2  5281.7 1056.24  5317.5  1061.8
#Mann= 5 ,-1 , 0
  4775.9     .12       0  5012.2     .07       0  5022.6     .12       0
  5155.4     .05       0  5281.7     .12       0
Bank Sta=5012.2,5022.6
XS Rating Curve= 0 ,0
Exp/Cntr=0.3,0.1

Chan Stop Cuts=-1
Use User Specified Reach Order=0
Composite Channel Slope=5