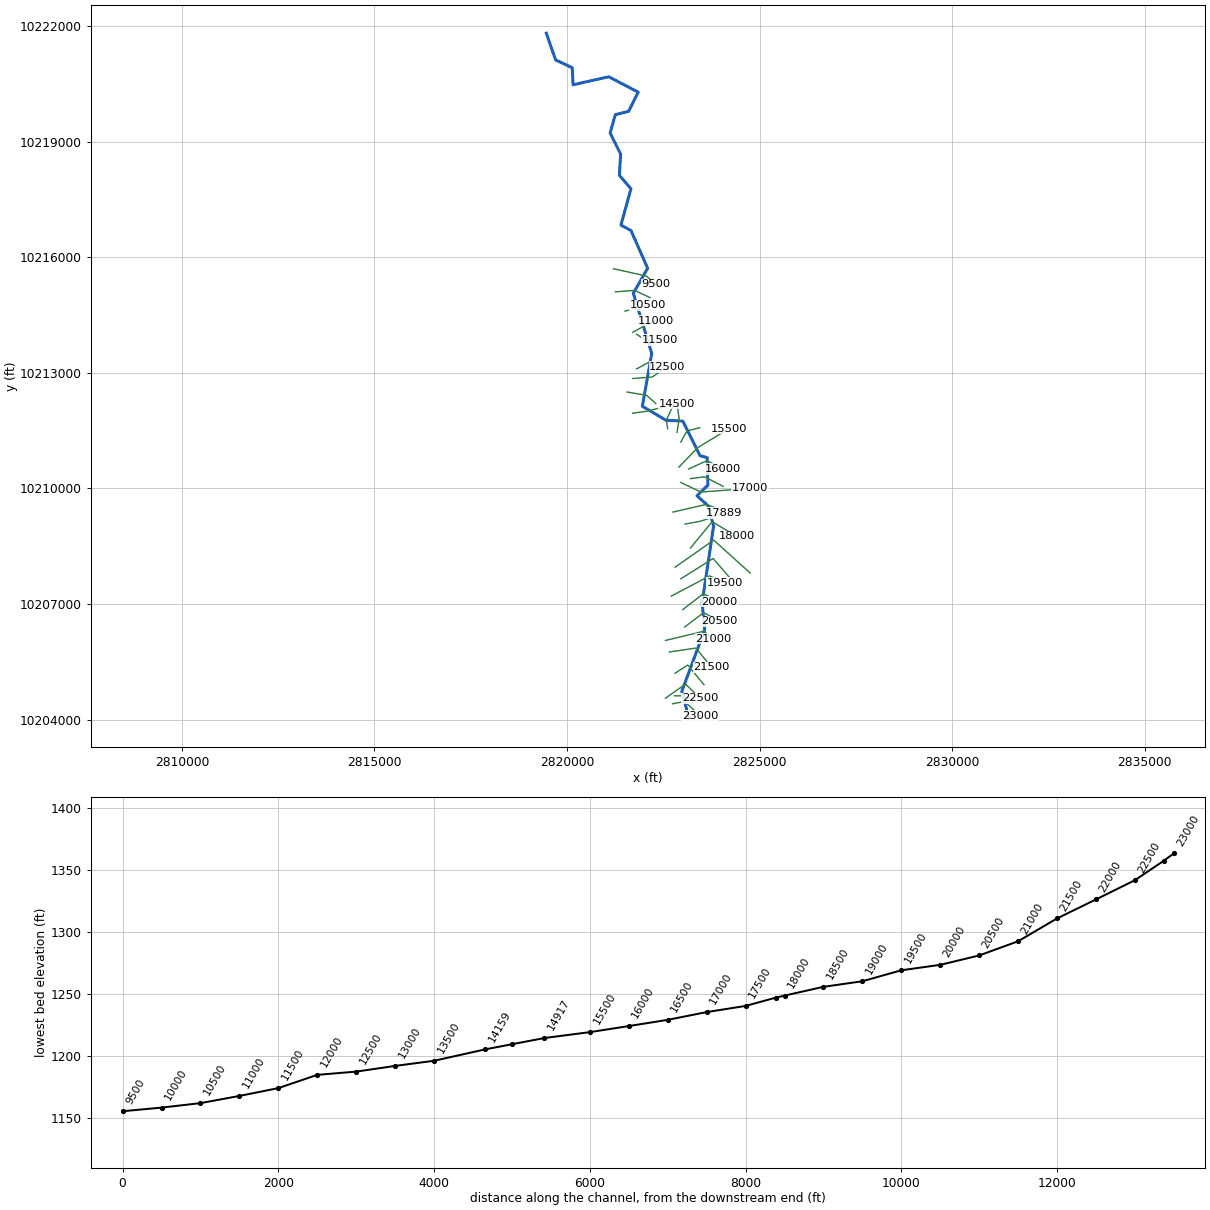
--- MULE MT BRANCH.prj (project) ---

Proj Title=MULE MT BRANCH Base Level Engineering
Current Plan=p01
Default Exp/Contr=0.3,0.1
English Units
Geom File=g01
Flow File=f01
Plan File=p01
Y Axis Title=Elevation
X Axis Title(PF)=Main Channel Distance
X Axis Title(XS)=Station
BEGIN DESCRIPTION:
MULE MT BRANCH
END DESCRIPTION:
DSS Export Rating Curves= 0
DSS Export Rating Curve Sorted= 0
DSS Export Volume Flow Curves= 0
DXF OffsetX= 0
DXF OffsetY= 0
DXF ScaleX= 1
DXF ScaleY= 10

--- MULE MT BRANCH.p01 (plan) ---

Plan Title=Multiple Run
Short Identifier=Multiple
Geom File=g01
Flow File=f01
Subcritical Flow
K Sum by GR= 0
Std Step Tol= 0.01
Critical Tol= 0.01
Num of Std Step Trials= 20
Max Error Tol= 0.3
Flow Tol Ratio= 0.001
Split Flow NTrial= 30
Split Flow Tol= 0.02
Split Flow Ratio= 0.02
Log Output Level= 0
Friction Slope Method= 1
Unsteady Friction Slope Method= 2
Unsteady Bridges Friction Slope Method= 1
Parabolic Critical Depth
Global Vel Dist=  1 , 1 , 1
Global Log Level= 0
CheckData=True
Encroach Param= -1, 0, 0, 0
BEGIN DESCRIPTION:
Multiple Run
END DESCRIPTION:

--- MULE MT BRANCH.f01 (steady flow) ---

Flow Title=Multiple
Number of Profiles=7
Profile Names=10-year,25-year,50-year,1pct_min,100-year,1pct_plu,500-year
River Rch & RM= MULE MT BRANCH,Reach-1,23000
     410     662    1558    1124    2227    4414    3313
River Rch & RM= MULE MT BRANCH,Reach-1,13500
     891    1521    3331    2075    4835   11265    7082
River Rch & RM= MULE MT BRANCH,Reach-1,3500
    1007    1737    3634    2522    5274   11031    7697
Boundary for River Rch & Prof#=MULE MT BRANCH,Reach-1,1
Up Type=0
Dn Type=3
Dn Slope=0.005
Boundary for River Rch & Prof#=MULE MT BRANCH,Reach-1,2
Up Type=0
Dn Type=3
Dn Slope=0.005
Boundary for River Rch & Prof#=MULE MT BRANCH,Reach-1,3
Up Type=0
Dn Type=3
Dn Slope=0.005
Boundary for River Rch & Prof#=MULE MT BRANCH,Reach-1,4
Up Type=0
Dn Type=3
Dn Slope=0.005
Boundary for River Rch & Prof#=MULE MT BRANCH,Reach-1,5
Up Type=0
Dn Type=3
Dn Slope=0.005
Boundary for River Rch & Prof#=MULE MT BRANCH,Reach-1,6
Up Type=0
Dn Type=3
Dn Slope=0.005
Boundary for River Rch & Prof#=MULE MT BRANCH,Reach-1,7
Up Type=0
Dn Type=3
Dn Slope=0.005

--- MULE MT BRANCH.g01 (geometry) ---

Geom Title=Existing Conditions
Program Version=4.10

River Reach=MULE MT BRANCH  ,Reach-1
Reach XY= 30
      2823166.25       10204025.       2822981.5       10204734.
        2823574.       10206329.        2823508.       10207037.
      2823805.25       10209017.      2823662.75       10209550.
        2823374.       10209809.      2823657.25       10210083.
      2823638.25       10210799.       2823452.5       10210847.
       2823008.5       10211747.        2822571.       10211769.
        2821956.       10212133.       2822199.5       10213505.
      2821721.75       10215067.        2822093.       10215716.
      2821661.75       10216694.      2821399.25       10216837.
       2821660.5       10217779.        2821360.       10218128.
      2821391.75       10218681.       2821119.5       10219226.
      2821253.75       10219701.      2821600.75       10219789.
      2821848.75       10220287.       2821084.5       10220687.
       2820157.5       10220479.       2820136.5       10220921.
      2819704.25       10221124.      2819461.75       10221819.

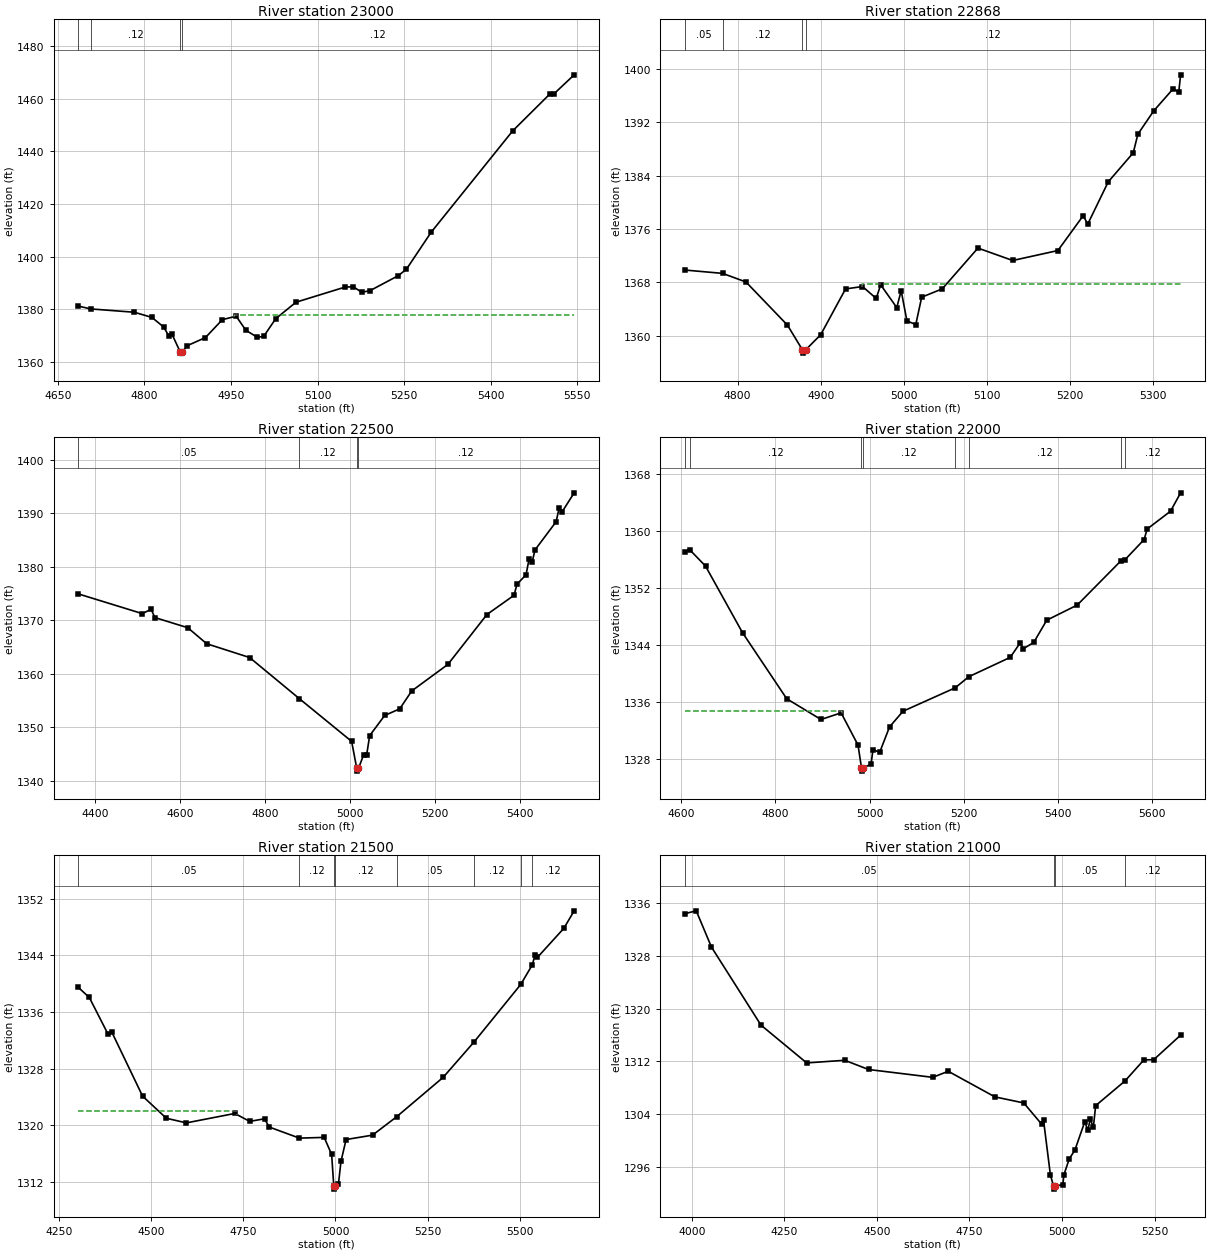
Type RM Length L Ch R = 1 ,23000   ,132,132,132
BEGIN DESCRIPTION:
MULE MT BRANCH 46.0
END DESCRIPTION:
XS GIS Cut Line= 3
      2822740.24      10204409.1      2823049.69     10204465.81
      2823455.67     10204103.12
#Sta/Elev= 30
  4685.4 1381.26  4707.1 1380.19  4782.4 1378.93  4812.9 1376.97  4833.3 1373.31
  4842.3 1369.89  4847.4 1370.72  4861.8 1363.91    4862 1363.41  4865.8 1363.91
  4873.9 1366.21  4905.7 1369.33  4934.9 1376.11  4958.8 1377.44  4975.6  1372.1
  4995.4 1369.43  5006.4 1369.73  5027.4 1376.49  5062.5 1382.74  5147.7  1388.5
    5162 1388.59  5176.2 1386.53  5190.4 1387.09  5239.7 1392.82  5253.9 1395.29
  5296.5 1409.26  5437.8 1447.76  5502.2 1461.77  5508.9 1461.74  5544.4 1469.07
#Mann= 4 ,-1 , 0
  4685.4     .05       0  4707.1     .12       0  4861.8     .07       0
  4865.8     .12       0
#XS Ineff= 2 , 0
                         4954.23         1377.98
Permanent Ineff=
       F       F
Bank Sta=4861.8,4865.8
XS Rating Curve= 0 ,0
Exp/Cntr=0.3,0.1

Type RM Length L Ch R = 1 ,22868   ,368,368,368
BEGIN DESCRIPTION:
Mapping XS 54061197
END DESCRIPTION:
XS GIS Cut Line= 3
      2822791.94     10204616.19      2823000.29     10204616.19
      2823363.85     10204477.69
#Sta/Elev= 30
  4736.3 1369.85  4781.8 1369.35    4810 1368.06    4860 1361.59    4878  1357.9
  4878.3  1357.4    4882  1357.9    4900 1360.15    4930 1367.02  4950.4 1367.38
  4966.9 1365.59  4972.3 1367.64  4991.7 1364.22    4997 1366.76  5003.9 1362.24
  5014.6 1361.68  5021.7 1365.78  5046.5 1367.03  5089.5 1373.14  5131.4 1371.28
  5185.8 1372.77  5216.4 1378.01  5221.7 1376.71  5246.5 1383.07  5276.6 1387.41
  5282.2 1390.21  5301.3  1393.7    5325 1397.05  5331.4 1396.47  5333.7  1399.1
#Mann= 4 ,-1 , 0
  4736.3     .05       0  4781.8     .12       0    4878     .07       0
    4882     .12       0
#XS Ineff= 2 , 0
                         4950.16         1367.78
Permanent Ineff=
       F       F
Bank Sta=4878,4882
XS Rating Curve= 0 ,0
Exp/Cntr=0.3,0.1

Type RM Length L Ch R = 1 ,22500   ,500,500,500
BEGIN DESCRIPTION:
MULE MT BRANCH 45.0
END DESCRIPTION:
XS GIS Cut Line= 3
      2822555.66      10204553.1      2823077.71      10204920.9
      2823455.69      10204553.1
#Sta/Elev= 30
  4361.4 1374.94  4511.7 1371.26  4532.7 1372.06  4541.3 1370.52  4618.8 1368.62
  4663.2 1365.63  4764.2 1363.05  4881.5 1355.34  5004.1 1347.38  5016.2 1342.32
  5016.5 1341.82  5020.2 1342.32  5032.4 1344.89  5039.3 1344.77  5046.5 1348.45
  5081.8 1352.22  5117.2 1353.46  5145.5 1356.81  5230.4 1361.76  5322.3 1371.09
    5386 1374.68    5393 1376.76  5414.3 1378.52  5421.3 1381.45  5428.5 1380.86
  5435.4 1383.17    5485 1388.43    5492 1390.97  5499.2 1390.29  5527.4 1393.83
#Mann= 4 ,-1 , 0
  4361.4     .05       0  4881.5     .12       0  5016.2     .07       0
  5020.2     .12       0
Bank Sta=5016.2,5020.2
XS Rating Curve= 0 ,0
Exp/Cntr=0.3,0.1

Type RM Length L Ch R = 1 ,22000   ,500,500,500
BEGIN DESCRIPTION:
MULE MT BRANCH 44.0
END DESCRIPTION:
XS GIS Cut Line= 3
      2822805.66     10205203.09      2823136.57     10205414.36
      2823555.69      10204903.1
#Sta/Elev= 30
  4607.4 1357.15  4617.4 1357.43  4651.4 1355.11  4730.1 1345.75    4824 1336.48
  4896.8 1333.57  4939.6  1334.5  4975.5 1329.98  4982.8 1326.82    4983 1326.32
  4986.8 1326.82  5003.2 1327.27  5007.3 1329.34  5021.6 1328.96  5042.5 1332.53
  5071.2 1334.73  5181.9 1338.01  5211.1 1339.58    5299 1342.29  5320.2 1344.33
  5326.7  1343.5  5348.9 1344.38  5376.6 1347.51  5441.3 1349.63  5533.9 1355.82
  5542.3 1355.96  5583.5 1358.83    5590 1360.31  5639.6 1362.81  5661.1 1365.39
#Mann= 8 ,-1 , 0
  4607.4     .05       0  4617.4     .12       0  4982.8     .07       0
  4986.8     .12       0  5181.9     .05       0  5211.1     .12       0
  5533.9     .05       0  5542.3     .12       0
#XS Ineff= 2 , 0
         4940.44 1334.71
Permanent Ineff=
       F       F
Bank Sta=4982.8,4986.8
XS Rating Curve= 0 ,0
Exp/Cntr=0.3,0.1

Type RM Length L Ch R = 1 ,21500   ,500,500,500
BEGIN DESCRIPTION:
MULE MT BRANCH 43.0
END DESCRIPTION:
XS GIS Cut Line= 3
      2822655.64      10205753.1      2823345.89     10205854.77
      2823755.71     10205353.08
#Sta/Elev= 30
  4302.3 1339.48  4332.1 1338.06  4383.2 1332.85  4393.3 1333.16  4476.6 1324.14
  4541.2 1321.01  4595.5 1320.36  4726.9 1321.69  4767.3 1320.57  4807.7 1320.94
    4820 1319.78  4902.1 1318.21  4969.5 1318.31  4989.7  1315.9  4995.4 1311.51
  4995.6 1311.01  4999.4 1311.51  5008.1 1311.68    5015 1314.92  5028.9 1318.01
  5100.7 1318.63  5165.7 1321.21  5292.4 1326.79  5375.8 1331.76  5502.9  1339.9
  5534.7 1342.71  5541.5  1344.1    5548 1343.71  5619.8 1347.82  5647.8 1350.29
#Mann= 8 ,-1 , 0
  4302.3     .05       0  4902.1     .12       0  4995.4     .07       0
  4999.4     .12       0  5165.7     .05       0  5375.8     .12       0
  5502.9     .05       0  5534.7     .12       0
#XS Ineff= 2 , 0
         4734.17 1322.09
Permanent Ineff=
       F       F
Bank Sta=4995.4,4999.4
XS Rating Curve= 0 ,0
Exp/Cntr=0.3,0.1

Type RM Length L Ch R = 1 ,21000   ,500,500,500
BEGIN DESCRIPTION:
MULE MT BRANCH 42.0
END DESCRIPTION:
XS GIS Cut Line= 3
      2822555.67     10206053.11      2823546.21     10206290.55
      2823805.69     10206103.11
#Sta/Elev= 30
  3981.4 1334.44  4012.3 1334.87  4053.4 1329.36  4187.1 1317.51  4310.5 1311.77
  4413.3 1312.17  4477.4 1310.77  4650.7 1309.58  4692.7  1310.5  4818.7 1306.61
  4896.6 1305.69  4944.8 1302.47  4949.9 1303.09  4968.6 1294.72  4976.9  1293.1
  4977.1  1292.6  4980.9  1293.1  5002.1 1293.25  5004.8 1294.75  5019.6 1297.23
  5034.3 1298.48  5061.3 1302.83  5069.8 1301.54    5076 1303.24  5084.5    1302
  5090.7 1305.28  5169.9 1309.03  5220.7 1312.22  5247.7 1312.27  5320.1 1315.99
#Mann= 4 ,-1 , 0
  3981.4     .05       0  4976.9     .05       0  4980.9     .05       0
  5169.9     .12       0
Bank Sta=4976.9,4980.9
XS Rating Curve= 0 ,0
Exp/Cntr=0.3,0.1

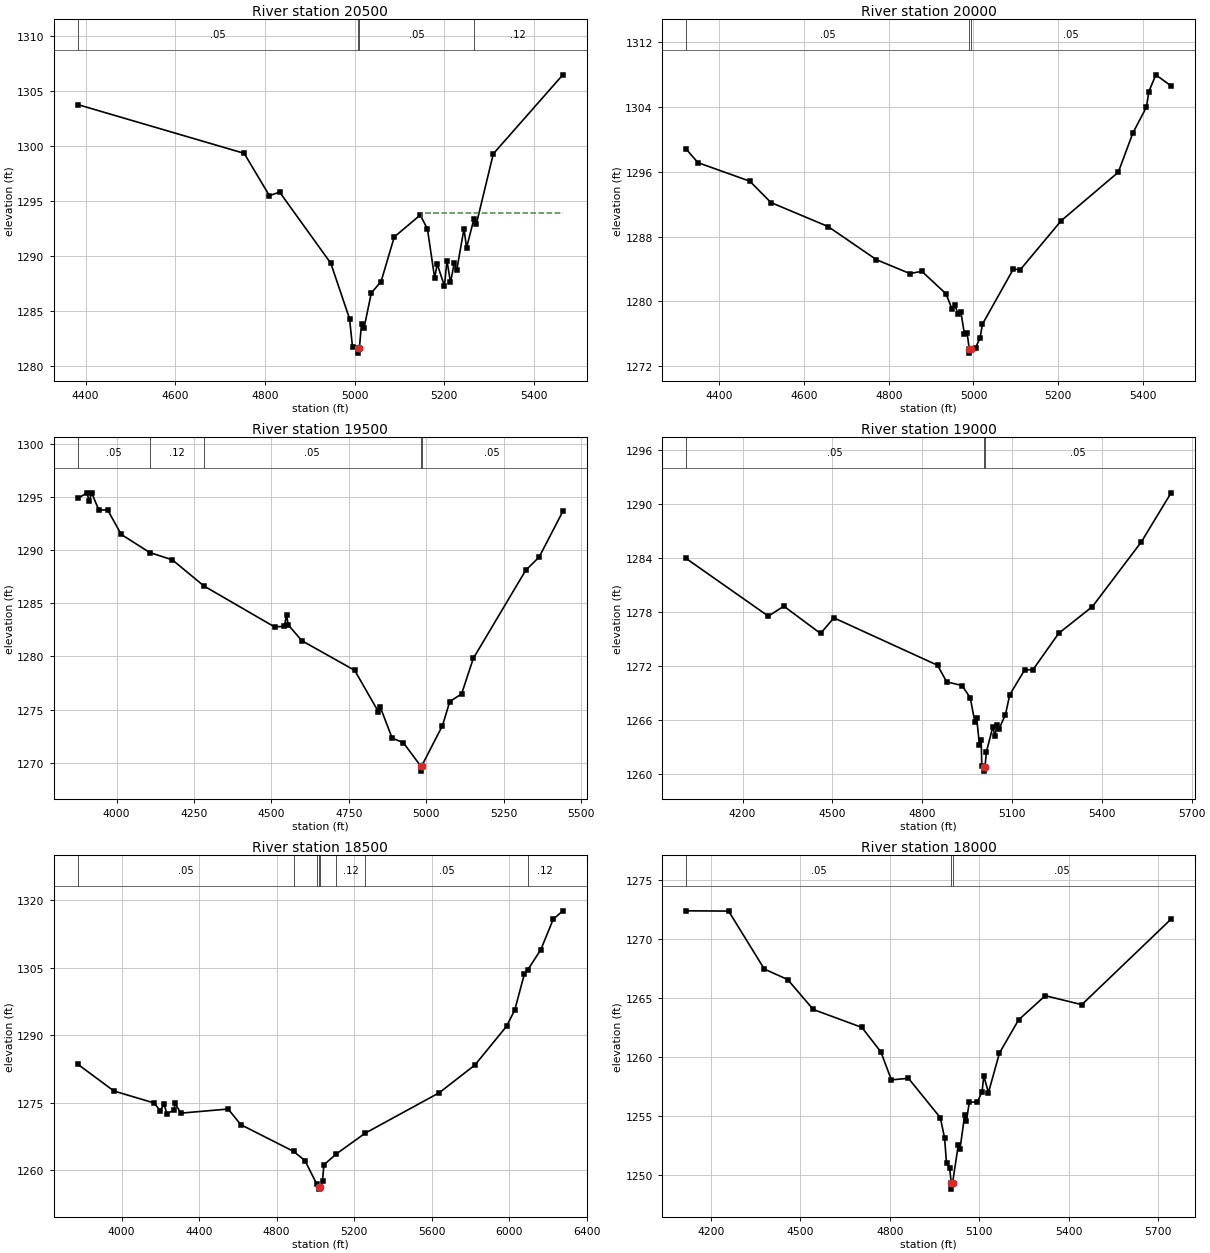
Type RM Length L Ch R = 1 ,20500   ,500,500,500
BEGIN DESCRIPTION:
MULE MT BRANCH 41.0
END DESCRIPTION:
XS GIS Cut Line= 3
       2823055.7     10206403.12      2823547.96     10206776.09
      2823955.67     10206553.12
#Sta/Elev= 30
  4382.4 1303.78  4753.7 1299.34  4809.9 1295.49  4832.8 1295.81    4947 1289.33
  4988.8 1284.28  4995.4 1281.71  5006.8 1281.65    5007 1281.15  5010.8 1281.65
  5015.6 1283.84  5021.3 1283.48  5037.4 1286.63  5059.2 1287.67  5088.6 1291.73
  5146.5 1293.72  5162.6 1292.46  5178.7 1287.99  5184.4 1289.27  5200.5 1287.26
  5206.2 1289.58    5214 1287.59  5222.4 1289.32  5228.1 1288.73  5244.2 1292.49
  5249.9 1290.74    5266 1293.32  5271.7  1292.9  5309.6  1299.3  5464.7 1306.49
#Mann= 4 ,-1 , 0
  4382.4     .05       0  5006.8     .05       0  5010.8     .05       0
    5266     .12       0
#XS Ineff= 2 , 0
                         5150.16         1293.92
Permanent Ineff=
       F       F
Bank Sta=5006.8,5010.8
XS Rating Curve= 0 ,0
Exp/Cntr=0.3,0.1

Type RM Length L Ch R = 1 ,20000   ,500,500,500
BEGIN DESCRIPTION:
MULE MT BRANCH 40.0
END DESCRIPTION:
XS GIS Cut Line= 3
      2823005.66      10206853.1      2823541.92     10207267.95
      2823955.67     10207053.12
#Sta/Elev= 30
    4322 1298.83  4350.1 1297.14  4472.4 1294.85  4522.2 1292.21  4657.1 1289.24
  4771.2 1285.14  4849.9 1283.43  4878.3  1283.7  4935.1 1280.93  4949.5 1279.03
  4955.9 1279.53    4964 1278.41  4970.4 1278.62  4978.5 1276.01  4984.9 1276.12
  4990.1 1274.09  4990.4 1273.59  4994.1 1274.09  5004.9 1274.24  5015.5 1275.47
  5021.2 1277.17  5094.4 1284.02  5109.7 1283.86  5207.1 1289.97  5341.7 1295.96
  5376.1 1300.82  5408.1 1304.01  5413.7 1305.93  5430.2    1308  5466.2 1306.63
#Mann= 3 ,-1 , 0
    4322     .05       0  4990.1     .05       0  4994.1     .05       0
Bank Sta=4990.1,4994.1
XS Rating Curve= 0 ,0
Exp/Cntr=0.3,0.1

Type RM Length L Ch R = 1 ,19500   ,500,500,500
BEGIN DESCRIPTION:
MULE MT BRANCH 39.0
END DESCRIPTION:
XS GIS Cut Line= 3
      2822705.65     10207203.09      2823701.06     10207728.16
      2824105.71      10207553.1
#Sta/Elev= 30
  3874.6 1294.89  3904.8 1295.41  3910.5 1294.67  3919.9 1295.37  3942.5 1293.79
  3970.9  1293.8    4015 1291.49  4106.7 1289.79  4179.8  1289.1  4281.8 1286.64
  4510.2 1282.78  4541.7 1282.84  4548.6 1283.89  4554.2 1282.97  4598.3 1281.48
  4768.8 1278.69  4845.6 1274.78  4851.2 1275.24  4889.6 1272.32  4926.1 1271.87
  4981.4  1269.7  4981.6  1269.2  4985.4  1269.7  5052.3 1273.49  5075.8 1275.75
    5114 1276.47  5151.7 1279.81    5321 1288.11  5364.6 1289.37  5440.9 1293.66
#Mann= 5 ,-1 , 0
  3874.6     .05       0  4106.7     .12       0  4281.8     .05       0
  4981.4     .05       0  4985.4     .05       0
Bank Sta=4981.4,4985.4
XS Rating Curve= 0 ,0
Exp/Cntr=0.3,0.1

Type RM Length L Ch R = 1 ,19000   ,500,500,500
BEGIN DESCRIPTION:
MULE MT BRANCH 38.0
END DESCRIPTION:
XS GIS Cut Line= 3
      2822955.72     10207653.14       2823792.3     10208180.25
      2824205.68     10207703.12
#Sta/Elev= 30
  4011.2 1283.97    4286 1277.56  4337.8 1278.67  4460.3 1275.64    4505 1277.37
  4851.1 1272.11  4881.7 1270.27  4933.1 1269.86  4960.5 1268.49  4975.8  1265.8
  4981.7 1266.31  4991.1 1263.31    4997 1263.77    4999 1260.91  5005.8 1260.86
  5006.1 1260.36  5009.8 1260.86  5014.4  1262.5  5035.9 1265.28  5042.9 1264.27
  5049.6 1265.44  5057.2 1265.09  5078.1 1266.64  5092.3 1268.83  5141.8 1271.58
  5170.2 1271.63  5255.7 1275.65  5368.7 1278.63  5532.1 1285.81  5631.3 1291.25
#Mann= 3 ,-1 , 0
  4011.2     .05       0  5005.8     .05       0  5009.8     .05       0
Bank Sta=5005.8,5009.8
XS Rating Curve= 0 ,0
Exp/Cntr=0.3,0.1

Type RM Length L Ch R = 1 ,18500   ,500,500,500
BEGIN DESCRIPTION:
MULE MT BRANCH 37.0
END DESCRIPTION:
XS GIS Cut Line= 3
      2822805.65     10207953.09      2823808.56      10208657.2
      2824755.65     10207803.14
#Sta/Elev= 30
  3774.6 1283.55  3960.7 1277.62    4169 1274.95  4198.6 1273.28  4219.5 1274.63
  4234.3 1272.57  4270.1 1273.39  4276.2 1274.85  4305.8 1272.71  4549.8 1273.62
  4615.2 1270.15  4887.8 1264.21  4945.4  1262.2  5005.8 1257.07  5020.4 1256.36
  5020.7 1255.86  5024.4 1256.36  5036.5 1257.71  5043.3 1261.24  5107.9 1263.68
  5256.5 1268.27  5638.2 1277.23  5822.1 1283.38    5985 1291.96  6027.6 1295.59
  6076.9 1303.55  6093.9 1304.43  6162.1 1308.99  6225.7 1315.69  6275.3 1317.57
#Mann= 8 ,-1 , 0
  3774.6     .05       0  4887.8     .12       0  5005.8     .05       0
  5020.4     .07       0  5024.4     .05       0  5107.9     .12       0
  5256.5     .05       0  6093.9     .12       0
Bank Sta=5020.4,5024.4
XS Rating Curve= 0 ,0
Exp/Cntr=0.3,0.1

Type RM Length L Ch R = 1 ,18000   ,111,111,111
BEGIN DESCRIPTION:
MULE MT BRANCH 36.0
END DESCRIPTION:
XS GIS Cut Line= 3
      2823205.67     10208453.09      2823768.06     10209134.74
      2824405.68     10208753.11
#Sta/Elev= 30
  4116.3 1272.39  4258.9 1272.37  4378.8 1267.45    4457 1266.56    4543 1264.02
  4705.9  1262.5  4769.7 1260.42  4804.9 1258.05  4862.2 1258.18  4969.1 1254.84
  4983.4 1253.12  4989.9 1250.96    5000 1250.61    5006 1249.28  5006.2 1248.78
    5010 1249.28  5029.4 1252.53  5035.2  1252.2  5050.8 1255.07  5056.6 1254.57
  5066.3 1256.15  5093.5 1256.17  5109.1 1257.06  5114.9 1258.38  5130.5 1256.97
  5167.5 1260.33  5231.6 1263.14  5321.1 1265.19  5443.6 1264.43  5743.1 1271.69
#Mann= 3 ,-1 , 0
  4116.3     .05       0    5006     .05       0    5010     .05       0
Bank Sta=5006,5010
XS Rating Curve= 0 ,0
Exp/Cntr=0.3,0.1

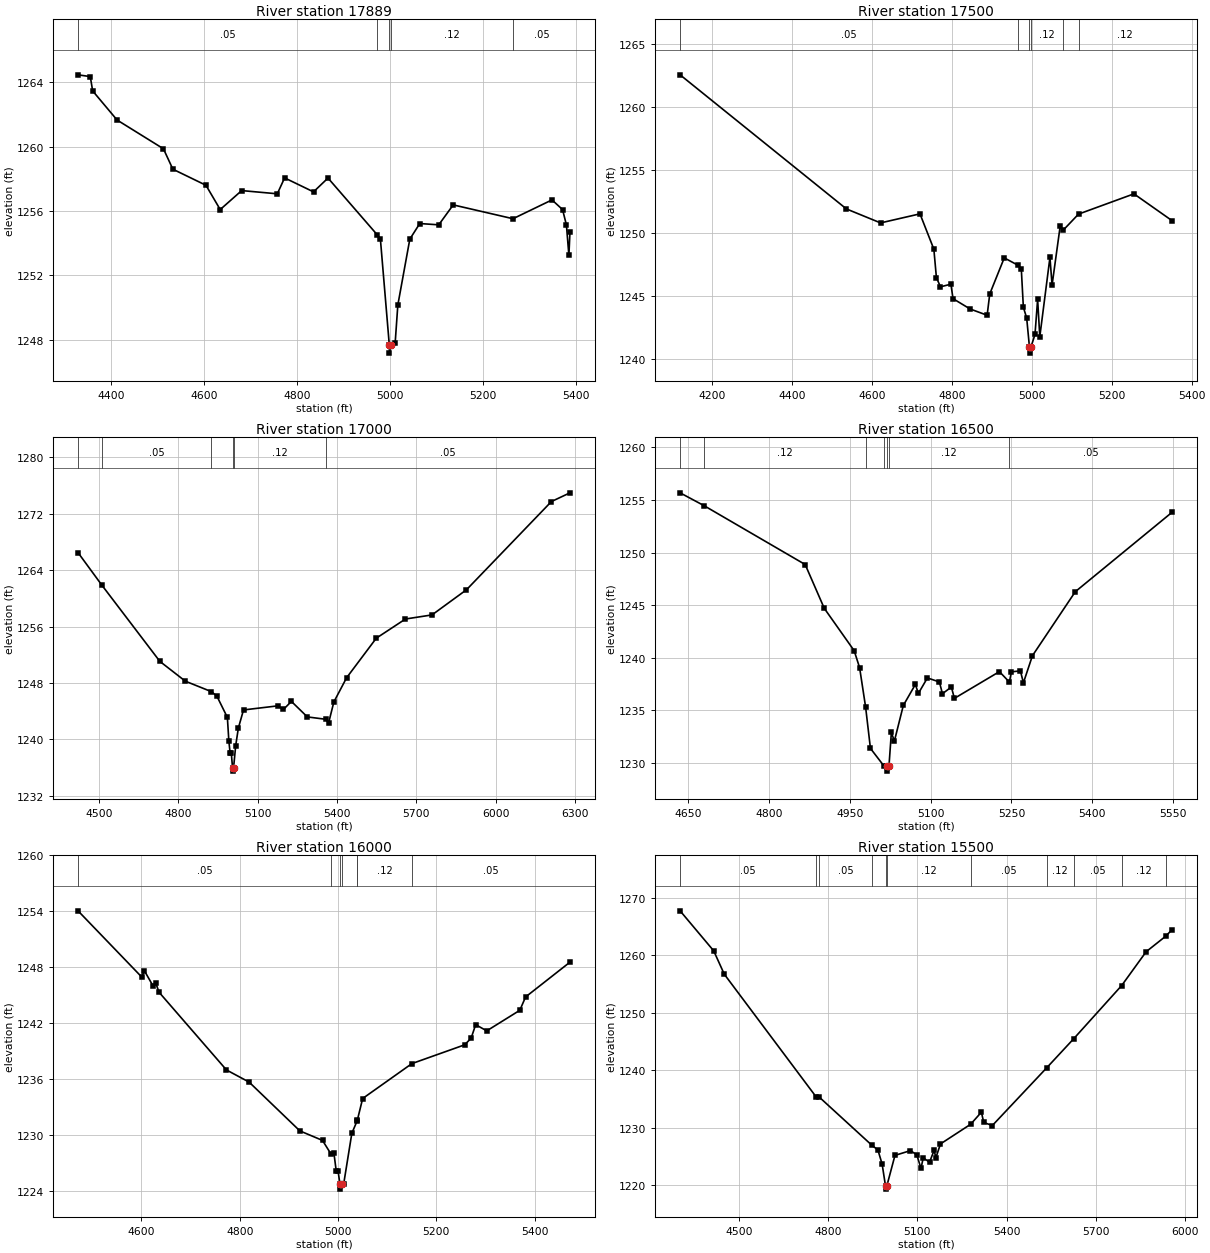
Type RM Length L Ch R = 1 ,17889   ,389,389,389
BEGIN DESCRIPTION:
Mapping XS d25fa260
END DESCRIPTION:
XS GIS Cut Line= 3
      2823065.17     10209073.17      2823481.79     10209151.29
      2824080.71     10209359.61
#Sta/Elev= 30
  4328.4 1264.47  4354.8 1264.36  4359.9 1263.47  4412.4 1261.66  4512.1 1259.87
  4532.4  1258.6  4603.6  1257.6  4634.2 1256.09  4680.4 1257.27    4757 1257.07
  4772.7 1258.06  4834.9 1257.19    4866 1258.05  4972.2 1254.51  4978.7 1254.26
  4997.9 1247.66  4998.2 1247.16  5001.9 1247.66  5010.5  1247.8  5016.2 1250.15
    5042 1254.25  5063.4 1255.22  5104.2 1255.14  5135.3 1256.38  5263.9 1255.52
  5347.7 1256.69  5370.5 1256.09  5378.8 1255.13  5384.1 1253.24  5386.4 1254.68
#Mann= 5 ,-1 , 0
  4328.4     .05       0  4972.2     .12       0  4997.9     .07       0
  5001.9     .12       0  5263.9     .05       0
Bank Sta=4997.9,5001.9
XS Rating Curve= 0 ,0
Exp/Cntr=0.3,0.1

Type RM Length L Ch R = 1 ,17500   ,500,500,500
BEGIN DESCRIPTION:
MULE MT BRANCH 35.0
END DESCRIPTION:
XS GIS Cut Line= 3
        2822751.      10209385.4      2823608.09     10209583.54
      2823938.46     10209465.26
#Sta/Elev= 30
  4120.3 1262.58  4536.4 1251.92  4621.8 1250.81  4720.4 1251.53  4755.1 1248.72
  4761.5 1246.46  4771.7 1245.73  4797.8 1245.94    4803 1244.79  4845.7 1243.97
  4888.4 1243.47  4894.9 1245.16  4931.2 1248.03  4966.6 1247.43  4973.9 1247.12
    4979 1244.11  4987.3 1243.25  4994.2 1240.96  4994.4 1240.46  4998.2 1240.96
  5008.1 1241.95  5014.7 1244.73  5020.1 1241.76  5045.5 1248.07  5050.8 1245.87
    5071 1250.53  5078.6 1250.23    5117 1251.51  5255.6 1253.12  5350.9 1250.99
#Mann= 6 ,-1 , 0
  4120.3     .05       0  4966.6     .12       0  4994.2     .07       0
  4998.2     .12       0  5078.6     .05       0    5117     .12       0
Bank Sta=4994.2,4998.2
XS Rating Curve= 0 ,0
Exp/Cntr=0.3,0.1

Type RM Length L Ch R = 1 ,17000   ,500,500,500
BEGIN DESCRIPTION:
MULE MT BRANCH 34.0
END DESCRIPTION:
XS GIS Cut Line= 3
      2822955.71      10210153.1      2823479.04     10209904.21
      2824755.71     10210003.11
#Sta/Elev= 30
  4420.5  1266.5  4510.1 1261.91  4729.9 1251.07  4826.3 1248.26  4924.5 1246.78
  4945.4 1246.15  4985.2 1243.12  4990.8 1239.78  4995.5  1238.1    5000  1238.1
  5004.7    1236  5004.9  1235.5  5008.7    1236  5016.7 1239.12  5026.7  1241.6
  5046.2 1244.18  5176.1 1244.76  5197.2 1244.25  5227.3 1245.39  5287.5 1243.19
  5358.3 1242.85  5367.7  1242.3  5387.8 1245.31  5435.9 1248.74  5548.3 1254.36
  5658.6 1257.08  5758.9 1257.66  5889.3 1261.23  6210.3 1273.74  6280.5 1274.98
#Mann= 6 ,-1 , 0
  4420.5     .12       0  4510.1     .05       0  4924.5     .12       0
  5004.7     .07       0  5008.7     .12       0  5358.3     .05       0
Bank Sta=5004.7,5008.7
XS Rating Curve= 0 ,0
Exp/Cntr=0.3,0.1

Type RM Length L Ch R = 1 ,16500   ,500,500,500
BEGIN DESCRIPTION:
MULE MT BRANCH 33.0
END DESCRIPTION:
XS GIS Cut Line= 3
      2823205.68     10210253.11      2823567.05      10210300.8
      2824055.66     10210053.12
#Sta/Elev= 30
  4635.5 1255.67    4680 1254.45  4867.5 1248.86  4902.9  1244.7  4958.3 1240.68
  4968.4 1239.07  4979.5 1235.34  4988.5  1231.4  5013.1 1229.76  5018.9 1229.74
  5019.1 1229.24  5022.9 1229.74  5027.3 1232.91  5032.9 1232.09  5049.5 1235.48
  5071.8 1237.47  5077.4 1236.62  5094.1 1238.09  5116.4 1237.71    5122 1236.59
  5138.6 1237.23  5144.2 1236.15  5227.7 1238.69  5246.1  1237.7    5250 1238.67
  5266.6 1238.76  5272.2 1237.63  5288.9  1240.2  5368.4 1246.28  5547.8 1253.82
#Mann= 7 ,-1 , 0
  4635.5     .05       0    4680     .12       0  4979.5     .05       0
  5013.1     .12       0  5018.9     .05       0  5022.9     .12       0
  5246.1     .05       0
Bank Sta=5018.9,5022.9
XS Rating Curve= 0 ,0
Exp/Cntr=0.3,0.1

Type RM Length L Ch R = 1 ,16000   ,500,500,500
BEGIN DESCRIPTION:
MULE MT BRANCH 32.0
END DESCRIPTION:
XS GIS Cut Line= 3
      2823155.72     10210503.13       2823637.4     10210722.04
      2824055.68     10210503.12
#Sta/Elev= 30
  4470.9 1254.05  4600.5 1246.96    4606 1247.63  4623.6    1246  4629.1 1246.33
  4635.6 1245.34    4773    1237  4819.1  1235.7  4922.4 1230.47  4968.5 1229.45
    4986 1227.97  4991.6 1228.14  4996.3 1226.22    5000 1226.22  5004.1 1224.73
  5004.3 1224.23  5008.1 1224.73  5011.7 1224.82  5028.2 1230.22  5039.1 1231.56
  5039.3  1231.6  5050.2 1233.94  5150.4 1237.68  5257.7 1239.69  5270.9  1240.4
  5280.2 1241.85  5302.8 1241.19    5370 1243.39  5381.8 1244.82  5472.1 1248.55
#Mann= 7 ,-1 , 0
  4470.9     .05       0    4986     .12       0  5004.1     .07       0
  5008.1     .12       0  5039.1     .05       0  5039.3     .12       0
  5150.4     .05       0
Bank Sta=5004.1,5008.1
XS Rating Curve= 0 ,0
Exp/Cntr=0.3,0.1

Type RM Length L Ch R = 1 ,15500   ,583,583,583
BEGIN DESCRIPTION:
MULE MT BRANCH 31.0
END DESCRIPTION:
XS GIS Cut Line= 3
      2822905.71     10210553.14      2823389.87     10211054.96
       2824205.7     10211553.12
#Sta/Elev= 30
  4302.7 1267.74  4415.7 1260.78  4451.2 1256.72  4759.6  1235.4  4771.1 1235.31
    4947 1226.98  4967.5 1226.15  4981.7 1223.68  4993.2 1219.84  4993.5 1219.34
  4997.2 1219.84  5024.8 1225.21    5077 1226.04  5098.3 1225.29  5112.3 1222.93
  5119.7 1224.78    5141 1224.03  5156.4 1226.09  5162.3  1224.8  5177.7  1227.2
  5279.1 1230.62  5315.2 1232.72  5323.2 1230.93    5352  1230.4  5534.2 1240.41
  5625.4 1245.49  5786.7 1254.75  5868.8 1260.62  5934.2 1263.31  5955.9 1264.46
#Mann= 11 ,-1 , 0
  4302.7     .05       0  4759.6     .12       0  4771.1     .05       0
    4947     .12       0  4993.2     .07       0  4997.2     .12       0
  5279.1     .05       0  5534.2     .12       0  5625.4     .05       0
  5786.7     .12       0  5934.2     .05       0
Bank Sta=4993.2,4997.2
XS Rating Curve= 0 ,0
Exp/Cntr=0.3,0.1

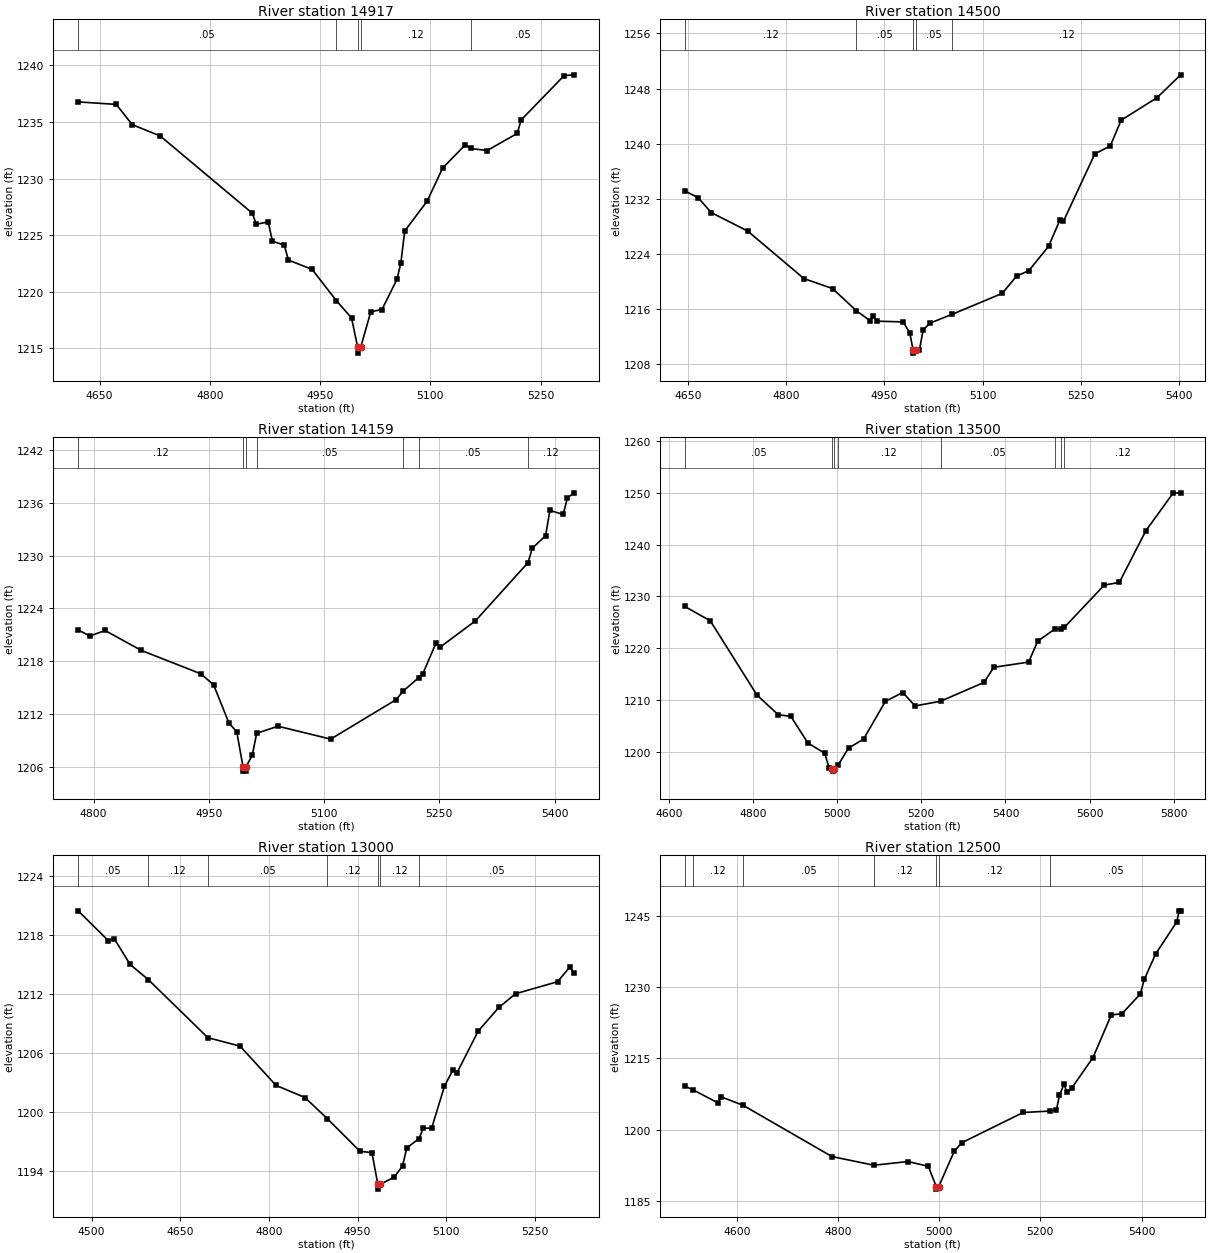
Type RM Length L Ch R = 1 ,14917   ,417,417,417
BEGIN DESCRIPTION:
MULE MT BRANCH 30.0
END DESCRIPTION:
XS GIS Cut Line= 3
      2822955.68     10211203.11      2823113.15     10211490.76
      2823448.88     10211576.37
#Sta/Elev= 30
    4621 1236.76  4672.7 1236.54  4694.5 1234.75  4732.4 1233.76  4857.6 1226.95
  4863.3 1225.96  4879.4 1226.17  4885.1 1224.47  4901.2 1224.12  4906.9  1222.8
  4939.1 1221.98    4972 1219.23  4992.8 1217.69  5001.1 1215.09  5001.4 1214.59
  5005.1 1215.09  5018.9 1218.24  5034.1 1218.44  5054.6 1221.11  5059.8 1222.56
  5065.1 1225.37  5095.5    1228  5116.7 1230.93  5147.6 1232.98  5154.6 1232.65
  5177.2 1232.47  5218.1 1233.98  5223.3 1235.16  5281.8 1239.08  5295.4 1239.15
#Mann= 5 ,-1 , 0
    4621     .05       0    4972     .12       0  5001.1     .07       0
  5005.1     .12       0  5154.6     .05       0
Bank Sta=5001.1,5005.1
XS Rating Curve= 0 ,0
Exp/Cntr=0.3,0.1

Type RM Length L Ch R = 1 ,14500   ,341,341,341
BEGIN DESCRIPTION:
MULE MT BRANCH 29.0
END DESCRIPTION:
XS GIS Cut Line= 3
      2822855.68     10211453.09       2822911.1     10211804.04
      2822855.68     10212203.11
#Sta/Elev= 30
  4644.7 1233.13    4665 1232.18  4685.2    1230  4740.9 1227.31    4827 1220.41
  4870.8 1218.96  4907.2 1215.73  4928.2  1214.3  4933.2    1215  4938.3 1214.23
  4978.8 1214.12  4988.9 1212.49  4993.7 1210.09  4993.9 1209.59  4997.7 1210.09
  5003.6 1210.09  5009.2 1212.95  5019.3 1213.93  5053.7 1215.23  5130.3 1218.27
    5152 1220.78  5170.7 1221.55    5201 1225.09  5218.6 1228.97  5223.7 1228.72
  5271.7 1238.51  5295.4 1239.68    5312  1243.4  5367.1 1246.69  5402.9 1249.99
#Mann= 5 ,-1 , 0
  4644.7     .12       0  4907.2     .05       0  4993.7     .05       0
  4997.7     .05       0  5053.7     .12       0
Bank Sta=4993.7,4997.7
XS Rating Curve= 0 ,0
Exp/Cntr=0.3,0.1

Type RM Length L Ch R = 1 ,14159   ,659,659,659
BEGIN DESCRIPTION:
MULE MT BRANCH 28.0
END DESCRIPTION:
XS GIS Cut Line= 3
      2822612.08     10211548.58      2822580.68     10211778.11
      2822755.69     10212153.12
#Sta/Elev= 30
    4780 1221.56    4795 1220.84  4814.9 1221.48  4862.2 1219.21  4939.4 1216.56
  4956.2 1215.31  4976.3 1210.93  4986.4 1209.95  4994.5 1205.98  4994.8 1205.48
  4998.3 1205.48  4998.5 1205.98  5006.6  1207.3  5012.3 1209.78    5040 1210.59
  5108.6 1209.12  5193.8 1213.61    5203 1214.58    5223  1216.1  5228.4 1216.52
  5245.8 1220.06  5251.3  1219.6    5297 1222.57  5365.6 1229.21  5371.1 1230.84
  5388.4 1232.26    5394 1235.14  5411.3 1234.68  5416.8 1236.57  5425.5 1237.14
#Mann= 7 ,-1 , 0
    4780     .12       0  4994.5     .07       0  4998.5     .12       0
  5012.3     .05       0    5203     .12       0    5223     .05       0
  5365.6     .12       0
Bank Sta=4994.5,4998.5
XS Rating Curve= 0 ,0
Exp/Cntr=0.3,0.1

Type RM Length L Ch R = 1 ,13500   ,500,500,500
BEGIN DESCRIPTION:
MULE MT BRANCH 27.0
END DESCRIPTION:
XS GIS Cut Line= 3
      2821705.64     10211953.11      2822064.71     10212001.41
      2822855.69     10212203.11
#Sta/Elev= 30
  4637.7 1228.05  4698.3 1225.29  4809.3 1210.95  4859.7 1207.16    4890 1206.82
  4930.4 1201.69  4970.5 1199.71  4980.8  1196.9  4988.6 1196.76  4988.9 1196.26
  4993.1 1196.76  5001.9 1197.38    5027 1200.72  5062.7 1202.43  5114.5 1209.73
  5155.8 1211.44  5185.3 1208.85  5245.7 1209.75  5348.8 1213.38  5372.5 1216.31
  5455.1 1217.31  5476.6 1221.35  5518.6 1223.76  5530.9  1223.7  5540.2 1224.04
  5634.9 1232.18  5670.6 1232.69  5733.7 1242.67  5798.4 1249.93  5816.3 1249.99
#Mann= 8 ,-1 , 0
  4637.7     .05       0  4988.6     .05       0  4993.1     .05       0
  5001.9     .12       0  5245.7     .05       0  5518.6     .12       0
  5530.9     .05       0  5540.2     .12       0
Bank Sta=4988.6,4993.1
XS Rating Curve= 0 ,0
Exp/Cntr=0.3,0.1

Type RM Length L Ch R = 1 ,13000   ,500,500,500
BEGIN DESCRIPTION:
MULE MT BRANCH 26.0
END DESCRIPTION:
XS GIS Cut Line= 3
      2821555.72     10212503.11       2822070.9     10212415.39
      2822305.67     10212203.12
#Sta/Elev= 30
  4477.4 1220.41  4528.1 1217.39  4538.2 1217.59  4565.2 1214.96  4595.9 1213.42
  4696.8 1207.51  4751.3 1206.65  4812.1 1202.66  4861.2 1201.42  4898.7 1199.29
  4954.1 1195.96  4974.4 1195.82  4984.4 1192.61  4984.7 1192.11  4988.9 1192.61
    5012 1193.32  5026.2 1194.47  5033.4  1196.3  5054.1 1197.25  5061.3 1198.31
  5075.5 1198.31  5097.2 1202.58  5111.4 1204.23  5118.1 1203.91    5154 1208.16
  5189.1 1210.58  5217.5 1211.98  5288.5  1213.2  5309.4  1214.7  5316.5 1214.05
#Mann= 7 ,-1 , 0
  4477.4     .05       0  4595.9     .12       0  4696.8     .05       0
  4898.7     .12       0  4984.4     .07       0  4988.9     .12       0
  5054.1     .05       0
Bank Sta=4984.4,4988.9
XS Rating Curve= 0 ,0
Exp/Cntr=0.3,0.1

Type RM Length L Ch R = 1 ,12500   ,500,500,500
BEGIN DESCRIPTION:
MULE MT BRANCH 25.0
END DESCRIPTION:
XS GIS Cut Line= 3
      2821705.68     10212853.11      2822206.98     10212890.66
      2822605.66     10213153.09
#Sta/Elev= 30
  4497.3 1209.16  4513.8 1208.39  4563.4 1205.62  4568.4 1206.96  4612.8 1205.13
  4788.1 1194.37  4871.2 1192.54  4938.5 1193.32  4978.6 1192.32  4994.5 1188.02
  4994.8 1187.52  4999.1 1188.02  5030.1 1195.53  5045.1 1197.29  5166.1 1203.63
  5219.5 1203.93  5231.9 1204.22  5237.9 1207.26  5246.9 1209.57  5252.9 1207.86
  5261.8 1208.72  5304.1 1215.18  5340.3 1224.14  5361.4 1224.39  5397.5 1228.52
  5405.5  1231.6  5427.7 1236.91  5469.8 1243.73  5474.3 1246.02  5477.3 1246.02
#Mann= 7 ,-1 , 0
  4497.3     .05       0  4513.8     .12       0  4612.8     .05       0
  4871.2     .12       0  4994.5     .07       0  4999.1     .12       0
  5219.5     .05       0
Bank Sta=4994.5,4999.1
XS Rating Curve= 0 ,0
Exp/Cntr=0.3,0.1

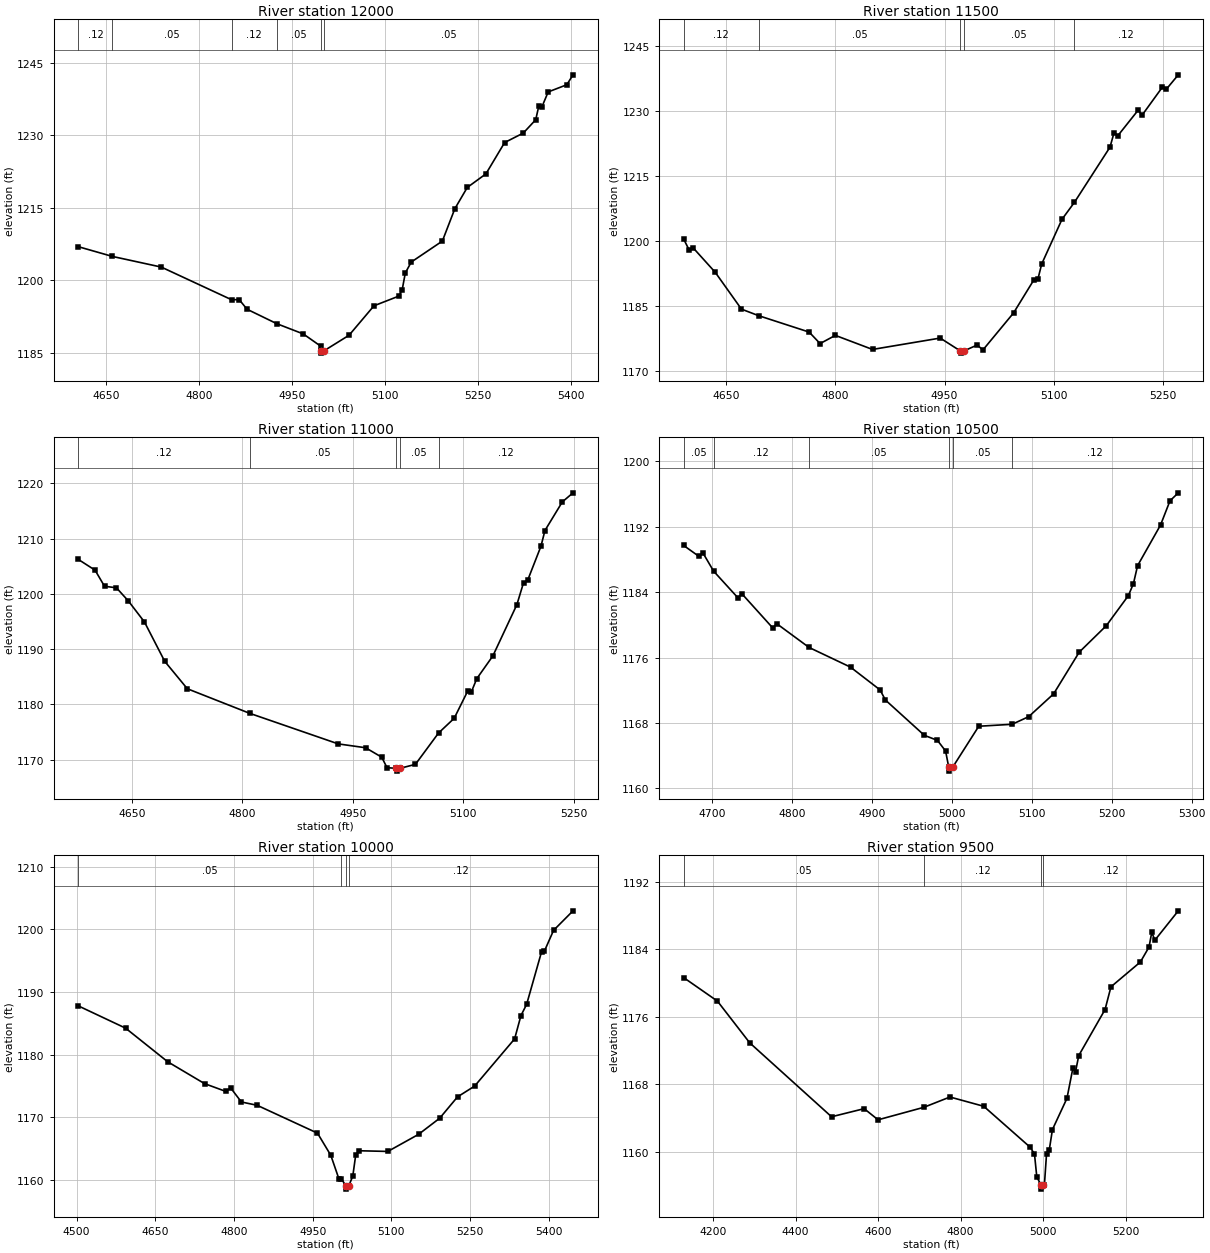
Type RM Length L Ch R = 1 ,12000   ,500,500,500
BEGIN DESCRIPTION:
MULE MT BRANCH 24.0
END DESCRIPTION:
XS GIS Cut Line= 3
      2821805.69     10213103.11      2822153.33      10213289.8
      2822555.66     10213253.11
#Sta/Elev= 30
  4605.4 1206.92  4660.6  1204.9  4739.4  1202.7  4852.8 1195.95  4865.2 1195.96
  4877.8 1193.98    4926 1190.98  4968.6 1188.87  4996.7 1186.34  4997.7  1185.4
    4998  1184.9  5002.3  1185.4  5042.5  1188.6  5082.7 1194.69  5122.9  1196.7
  5128.3 1198.05  5133.3 1201.49  5142.9 1203.74  5193.1 1208.08  5213.2 1214.76
  5233.3 1219.17  5263.4 1221.98  5293.6 1228.46  5323.7 1230.42  5343.8 1233.18
  5348.9  1236.1  5353.9 1235.87  5363.9 1238.93    5394 1240.42    5404 1242.47
#Mann= 6 ,-1 , 0
  4605.4     .12       0  4660.6     .05       0  4852.8     .12       0
    4926     .05       0  4997.7     .05       0  5002.3     .05       0
Bank Sta=4997.7,5002.3
XS Rating Curve= 0 ,0
Exp/Cntr=0.3,0.1

Type RM Length L Ch R = 1 ,11500   ,500,500,500
BEGIN DESCRIPTION:
MULE MT BRANCH 23.0
END DESCRIPTION:
XS GIS Cut Line= 3
      2821805.67     10214003.12      2822145.63     10213775.91
      2822405.71     10213853.12
#Sta/Elev= 30
  4591.1 1200.57  4598.6 1198.05  4604.6 1198.43  4634.7 1192.84  4670.7 1184.36
  4694.2 1182.86  4763.8 1179.07  4778.8 1176.42  4799.8 1178.31  4850.9 1175.07
    4944 1177.69  4971.7 1174.72    4972 1174.22  4976.4 1174.72    4995  1176.1
  5002.6 1174.93  5044.9  1183.5  5072.9 1191.15  5078.2 1191.22  5083.5 1194.76
  5111.4 1205.06  5128.5 1208.97  5177.4 1221.69    5183 1225.04  5188.2 1224.33
  5216.2 1230.23  5221.4 1229.03  5249.4 1235.51  5254.7 1235.01  5271.3 1238.36
#Mann= 5 ,-1 , 0
  4591.1     .12       0  4694.2     .05       0  4971.7     .05       0
  4976.4     .05       0  5128.5     .12       0
Bank Sta=4971.7,4976.4
XS Rating Curve= 0 ,0
Exp/Cntr=0.3,0.1

Type RM Length L Ch R = 1 ,11000   ,500,500,500
BEGIN DESCRIPTION:
MULE MT BRANCH 22.0
END DESCRIPTION:
XS GIS Cut Line= 3
      2821705.69     10214053.12      2822076.98     10214254.94
       2822305.7     10214353.12
#Sta/Elev= 30
  4577.4 1206.23  4600.2 1204.28    4613 1201.37  4629.2 1201.09  4645.3 1198.72
  4667.2 1194.91  4694.7 1187.79  4725.4 1182.82  4810.1 1178.37  4930.2 1172.84
  4967.4 1172.14  4989.3 1170.43  4996.4 1168.54    5009 1168.41  5009.4 1167.91
  5013.9 1168.41    5035 1169.14  5066.4 1174.81  5087.6 1177.47  5105.7 1182.33
  5111.1 1182.31  5118.3 1184.65  5140.1 1188.76  5172.7 1198.04  5181.8 1202.04
  5187.3 1202.44  5205.4 1208.62  5210.8 1211.46  5234.4 1216.64  5248.9 1218.28
#Mann= 5 ,-1 , 0
  4577.4     .12       0  4810.1     .05       0    5009     .05       0
  5013.9     .05       0  5066.4     .12       0
Bank Sta=5009,5013.9
XS Rating Curve= 0 ,0
Exp/Cntr=0.3,0.1

Type RM Length L Ch R = 1 ,10500   ,500,500,500
BEGIN DESCRIPTION:
MULE MT BRANCH 21.0
END DESCRIPTION:
XS GIS Cut Line= 3
      2821505.73     10214603.12      2821833.17     10214675.77
       2822105.7     10214753.12
#Sta/Elev= 30
  4664.6 1189.72  4683.8 1188.38  4688.9 1188.79  4702.2 1186.57  4732.5 1183.32
  4737.6  1183.8    4776 1179.64  4781.2 1180.14  4821.5 1177.24  4873.4 1174.83
  4910.4 1172.04    4917 1170.81  4965.7 1166.49  4982.1 1165.87  4992.3 1164.57
  4996.2 1162.61  4996.6 1162.11  5001.3 1162.61  5033.8  1167.6  5075.5 1167.84
  5096.2 1168.77  5127.4 1171.56  5159.4 1176.66  5193.3  1179.9  5220.9 1183.58
  5227.2 1185.04  5232.4 1187.24  5261.1 1192.21  5272.9 1195.17  5283.3 1196.15
#Mann= 6 ,-1 , 0
  4664.6     .05       0  4702.2     .12       0  4821.5     .05       0
  4996.2     .05       0  5001.3     .05       0  5075.5     .12       0
Bank Sta=4996.2,5001.3
XS Rating Curve= 0 ,0
Exp/Cntr=0.3,0.1

Type RM Length L Ch R = 1 ,10000   ,500,500,500
BEGIN DESCRIPTION:
MULE MT BRANCH 20.0
END DESCRIPTION:
XS GIS Cut Line= 3
      2821255.72     10215103.11      2821751.15     10215141.28
      2822155.72     10214953.09
#Sta/Elev= 30
  4503.1 1187.77  4593.3 1184.21  4673.6 1178.84  4743.8 1175.35  4783.9 1174.12
  4793.9 1174.63    4814 1172.42  4844.1 1171.89  4959.1 1167.44  4984.5  1163.9
  4999.8 1160.17  5004.6 1160.14  5013.5    1159  5013.9  1158.5  5018.6    1159
  5026.4 1160.58  5031.9 1163.92  5038.1 1164.63  5093.2 1164.52  5151.8 1167.25
  5192.1 1169.83    5226 1173.23  5258.7 1174.96  5334.9  1182.5  5346.9 1186.21
  5357.8 1188.02  5386.2  1196.4  5391.7 1196.52  5409.1 1199.83  5446.2 1202.95
#Mann= 4 ,-1 , 0
  4503.1     .05       0  5004.6     .12       0  5013.5     .05       0
  5018.6     .12       0
Bank Sta=5013.5,5018.6
XS Rating Curve= 0 ,0
Exp/Cntr=0.3,0.1

Type RM Length L Ch R = 1 ,9500    ,500,500,500
BEGIN DESCRIPTION:
MULE MT BRANCH 19.0
END DESCRIPTION:
XS GIS Cut Line= 3
      2821205.65     10215703.12      2822056.36     10215514.82
       2822305.7      10215303.1
#Sta/Elev= 30
  4128.7 1180.64  4210.7 1177.85  4289.1  1172.9  4487.2 1164.15  4566.2 1165.11
  4599.9 1163.79  4710.8 1165.27    4774 1166.49  4855.9 1165.39  4968.6 1160.53
  4978.8 1159.72  4984.4 1157.02  4994.5 1156.08  4994.9 1155.58  4999.6 1156.08
  5002.8 1156.08    5008 1159.78  5014.6 1160.23  5022.3 1162.64  5057.4 1166.33
  5071.7 1169.88  5078.3 1169.51    5086  1171.4  5149.7 1176.85    5164 1179.54
  5235.3 1182.48  5256.2 1184.25  5262.8 1185.98  5270.5 1185.07  5327.1 1188.54
#Mann= 4 ,-1 , 0
  4128.7     .05       0  4710.8     .12       0  4994.5     .07       0
  4999.6     .12       0
Bank Sta=4994.5,4999.6
XS Rating Curve= 0 ,0
Exp/Cntr=0.3,0.1