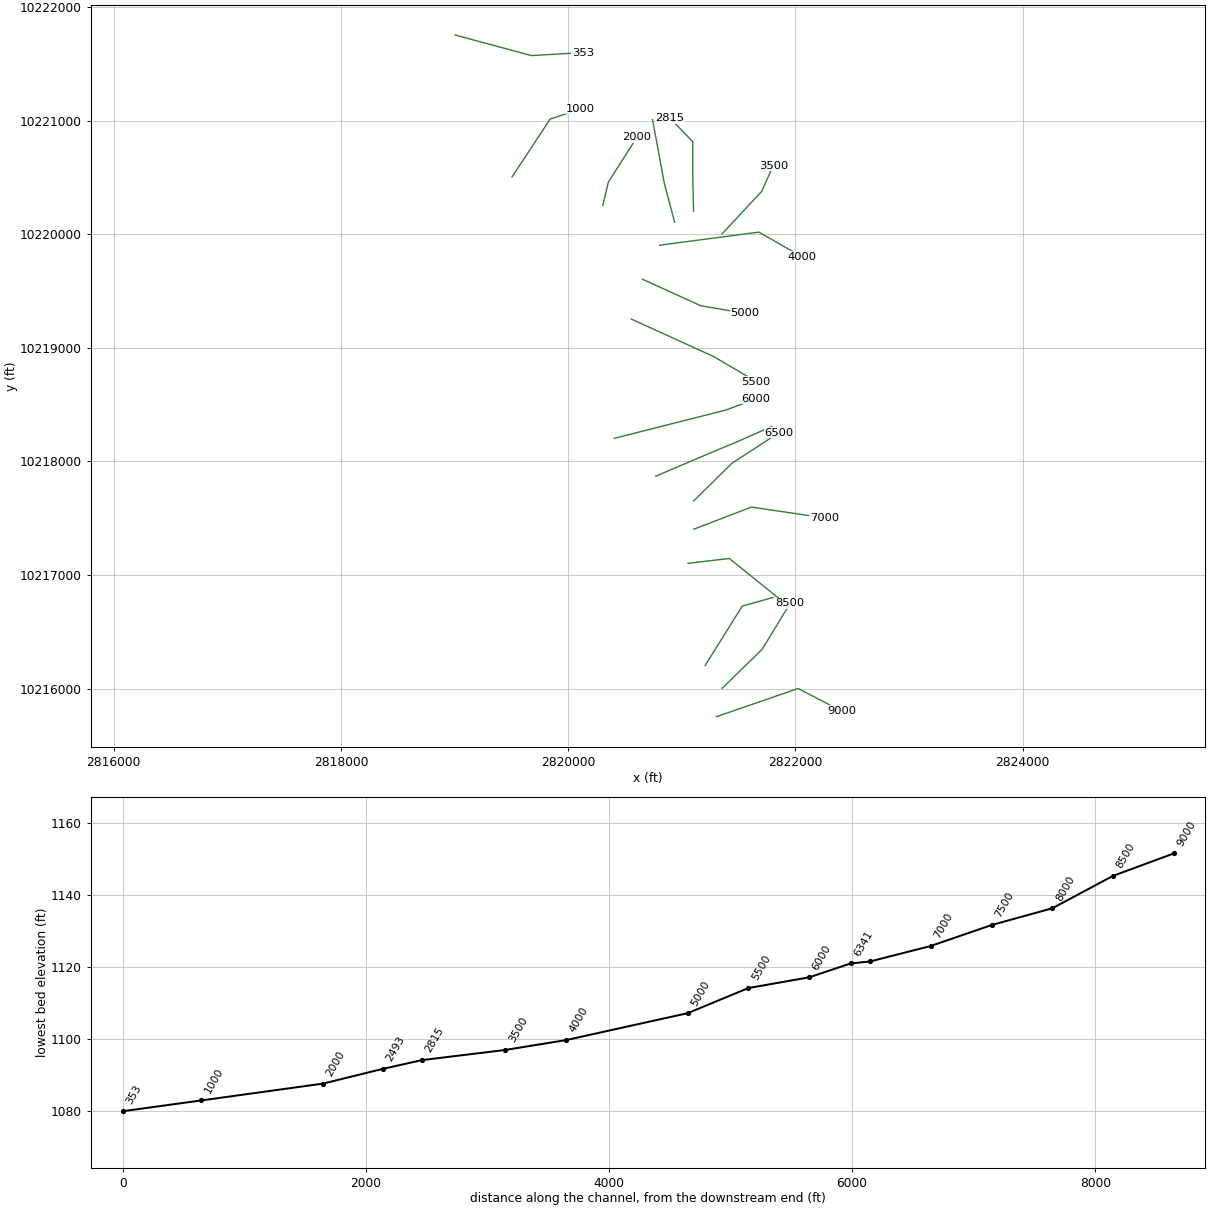
HEC-RAS study MULE MT BRANCH.prj: MULE MT BRANCH Base Level Engineering

--- MULE MT BRANCH.g01 (geometry) --- (continued)

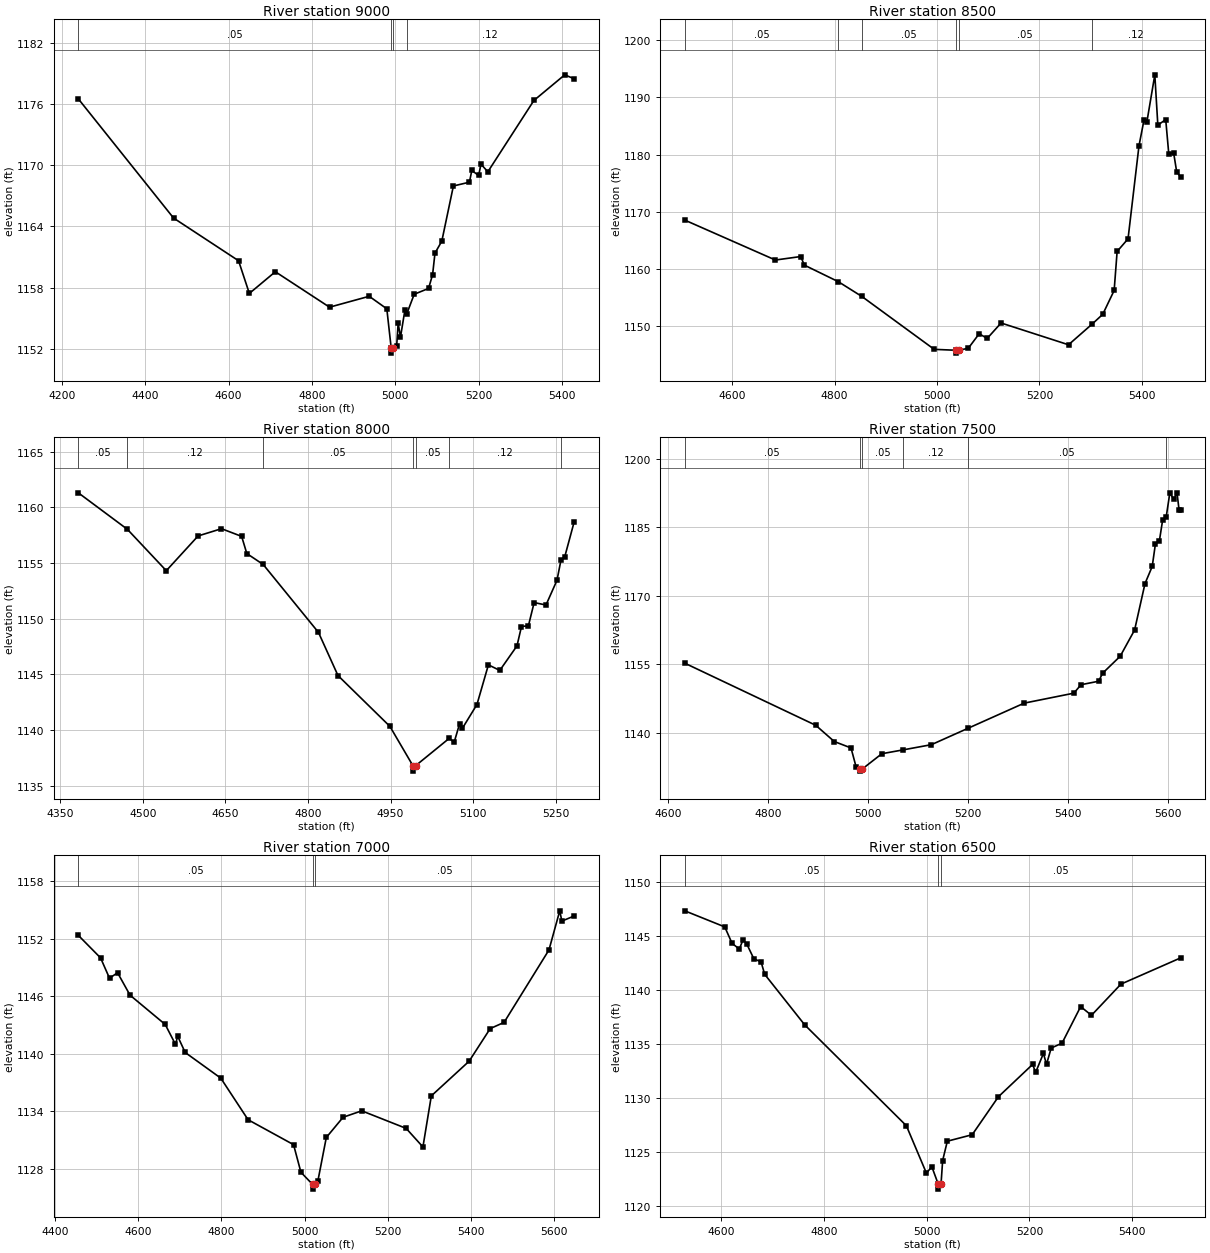
Type RM Length L Ch R = 1 ,9000    ,500,500,500
BEGIN DESCRIPTION:
MULE MT BRANCH 18.0
END DESCRIPTION:
XS GIS Cut Line= 3
      2821305.69     10215753.11      2822024.83      10216001.4
      2822405.71      10215803.1
#Sta/Elev= 30
  4239.2 1176.52  4467.8 1164.82  4623.8 1160.63  4649.7 1157.42  4712.1 1159.55
  4842.2 1156.07  4937.4 1157.14  4979.7 1155.91  4990.2 1152.06  4990.6 1151.56
  4995.4 1152.06  5003.3 1152.23  5006.9 1154.51  5012.5 1153.13  5023.3 1155.83
  5027.1 1155.36  5045.4 1157.34  5079.9 1157.91  5089.6 1159.27  5095.3 1161.38
  5111.7 1162.55  5139.5 1167.97    5178 1168.34  5183.7 1169.49  5200.1    1169
  5205.8 1170.11  5222.2 1169.36  5332.7 1176.36  5406.8 1178.88  5429.4 1178.49
#Mann= 4 ,-1 , 0
  4239.2     .05       0  4990.2     .05       0  4995.4     .05       0
  5027.1     .12       0
Bank Sta=4990.2,4995.4
XS Rating Curve= 0 ,0
Exp/Cntr=0.3,0.1

Type RM Length L Ch R = 1 ,8500    ,500,500,500
BEGIN DESCRIPTION:
MULE MT BRANCH 17.0
END DESCRIPTION:
XS GIS Cut Line= 3
      2821355.65     10216003.08      2821708.51     10216346.66
      2821955.68      10216753.1
#Sta/Elev= 30
  4507.5 1168.55  4684.4 1161.58  4733.8 1162.19    4741 1160.69  4807.3  1157.8
  4853.3 1155.22  4994.5 1145.99  5037.1 1145.83  5037.5 1145.33  5042.3 1145.83
  5061.1 1146.18  5082.4 1148.72  5097.9 1147.89  5125.1 1150.59  5256.8 1146.79
  5302.4 1150.36  5323.6  1152.1  5345.9 1156.27  5351.7 1163.08    5373 1165.28
  5394.4 1181.53    5404 1185.94  5409.8 1185.68  5425.3 1193.91  5431.2 1185.13
  5446.6  1186.1  5452.5 1180.17  5462.1 1180.27    5468 1176.99  5475.7 1176.08
#Mann= 6 ,-1 , 0
  4507.5     .05       0  4807.3     .12       0  4853.3     .05       0
  5037.1     .05       0  5042.3     .05       0  5302.4     .12       0
Bank Sta=5037.1,5042.3
XS Rating Curve= 0 ,0
Exp/Cntr=0.3,0.1

Type RM Length L Ch R = 1 ,8000    ,500,500,500
BEGIN DESCRIPTION:
MULE MT BRANCH 16.0
END DESCRIPTION:
XS GIS Cut Line= 3
      2821205.66     10216203.08      2821532.65     10216726.54
      2821805.72     10216803.12
#Sta/Elev= 30
  4382.8  1161.3    4472 1158.02  4542.6 1154.31  4600.4 1157.43  4642.9 1158.08
  4679.5 1157.39  4688.9 1155.85  4718.6 1154.87  4819.1 1148.77  4854.5  1144.9
  4948.8 1140.34  4990.5 1136.82  4990.9 1136.32  4995.9 1136.82  5056.8 1139.27
  5065.5 1138.89  5075.3 1140.55  5080.5 1140.16    5107  1142.3  5127.8 1145.86
  5148.5 1145.36  5179.7 1147.56  5187.9  1149.3  5200.5 1149.37  5210.9 1151.45
  5232.4 1151.23  5252.4 1153.45  5259.5 1155.23  5266.5 1155.56  5283.6 1158.69
#Mann= 7 ,-1 , 0
  4382.8     .05       0    4472     .12       0  4718.6     .05       0
  4990.5     .05       0  4995.9     .05       0  5056.8     .12       0
  5259.5     .05       0
Bank Sta=4990.5,4995.9
XS Rating Curve= 0 ,0
Exp/Cntr=0.3,0.1

Type RM Length L Ch R = 1 ,7500    ,500,500,500
BEGIN DESCRIPTION:
MULE MT BRANCH 15.0
END DESCRIPTION:
XS GIS Cut Line= 3
      2821055.66     10217103.11      2821419.17     10217145.73
       2821905.7      10216753.1
#Sta/Elev= 30
    4634 1155.28  4895.8 1141.69  4932.8 1138.14  4966.3 1136.73  4976.4  1132.6
  4983.6 1132.16  4984.1 1131.66  4989.2 1132.16  5027.9 1135.47  5069.4 1136.29
    5127 1137.45  5200.7 1141.06  5312.5 1146.54  5411.7 1148.72  5426.1 1150.57
  5461.3 1151.33  5469.2 1153.08  5504.4  1156.8  5533.2 1162.54    5554 1172.71
  5568.4 1176.44  5574.8 1181.37  5582.8  1182.1  5589.2 1186.57  5596.4 1187.32
  5603.6 1192.51  5611.6 1191.16    5618 1192.56    5622 1188.89  5625.2 1188.89
#Mann= 6 ,-1 , 0
    4634     .05       0  4983.6     .05       0  4989.2     .05       0
  5069.4     .12       0  5200.7     .05       0  5596.4     .12       0
Bank Sta=4983.6,4989.2
XS Rating Curve= 0 ,0
Exp/Cntr=0.3,0.1

Type RM Length L Ch R = 1 ,7000    ,500,500,500
BEGIN DESCRIPTION:
MULE MT BRANCH 14.0
END DESCRIPTION:
XS GIS Cut Line= 3
      2821105.69     10217403.12      2821613.94     10217598.19
      2822255.64     10217503.12
#Sta/Elev= 30
  4455.6 1152.33  4509.1 1149.98  4530.6 1147.86    4550 1148.43    4580 1146.09
  4664.7 1143.03  4689.3 1140.96  4694.7  1141.8  4712.7 1140.11  4798.4 1137.43
  4864.1 1133.09  4973.5 1130.49  4991.2 1127.61  5019.1 1126.35  5019.6 1125.85
  5024.8 1126.35  5032.1 1126.72  5052.3 1131.24  5092.7 1133.35  5137.6 1134.02
  5244.4 1132.19  5284.8 1130.25    5305 1135.58    5396  1139.2  5446.6  1142.6
  5480.1 1143.25  5588.1 1150.81    5614 1154.89  5619.1 1153.82  5648.7 1154.35
#Mann= 3 ,-1 , 0
  4455.6     .05       0  5019.1     .05       0  5024.8     .05       0
Bank Sta=5019.1,5024.8
XS Rating Curve= 0 ,0
Exp/Cntr=0.3,0.1

Type RM Length L Ch R = 1 ,6500    ,159,159,159
BEGIN DESCRIPTION:
MULE MT BRANCH 13.0
END DESCRIPTION:
XS GIS Cut Line= 3
      2821105.66     10217653.09      2821441.52     10217983.31
      2821855.69     10218253.11
#Sta/Elev= 30
    4529 1147.32  4606.8 1145.83    4621 1144.31  4635.1 1143.78  4642.1  1144.6
  4649.2 1144.29  4663.4 1142.88  4677.5 1142.59  4684.5 1141.44  4762.4 1136.76
  4960.4 1127.41  4999.4 1123.02  5009.9 1123.62  5022.1 1122.04  5022.5 1121.54
  5027.9 1122.04    5031 1124.19  5040.1 1125.98  5088.5 1126.58  5139.6  1130.1
  5206.1 1133.09  5212.1 1132.36  5227.2 1134.11  5233.2  1133.1  5242.3 1134.61
  5263.4 1135.06  5299.7 1138.45  5320.7 1137.64  5378.1 1140.53  5494.3 1142.96
#Mann= 3 ,-1 , 0
    4529     .05       0  5022.1     .05       0  5027.9     .05       0
Bank Sta=5022.1,5027.9
XS Rating Curve= 0 ,0
Exp/Cntr=0.3,0.1

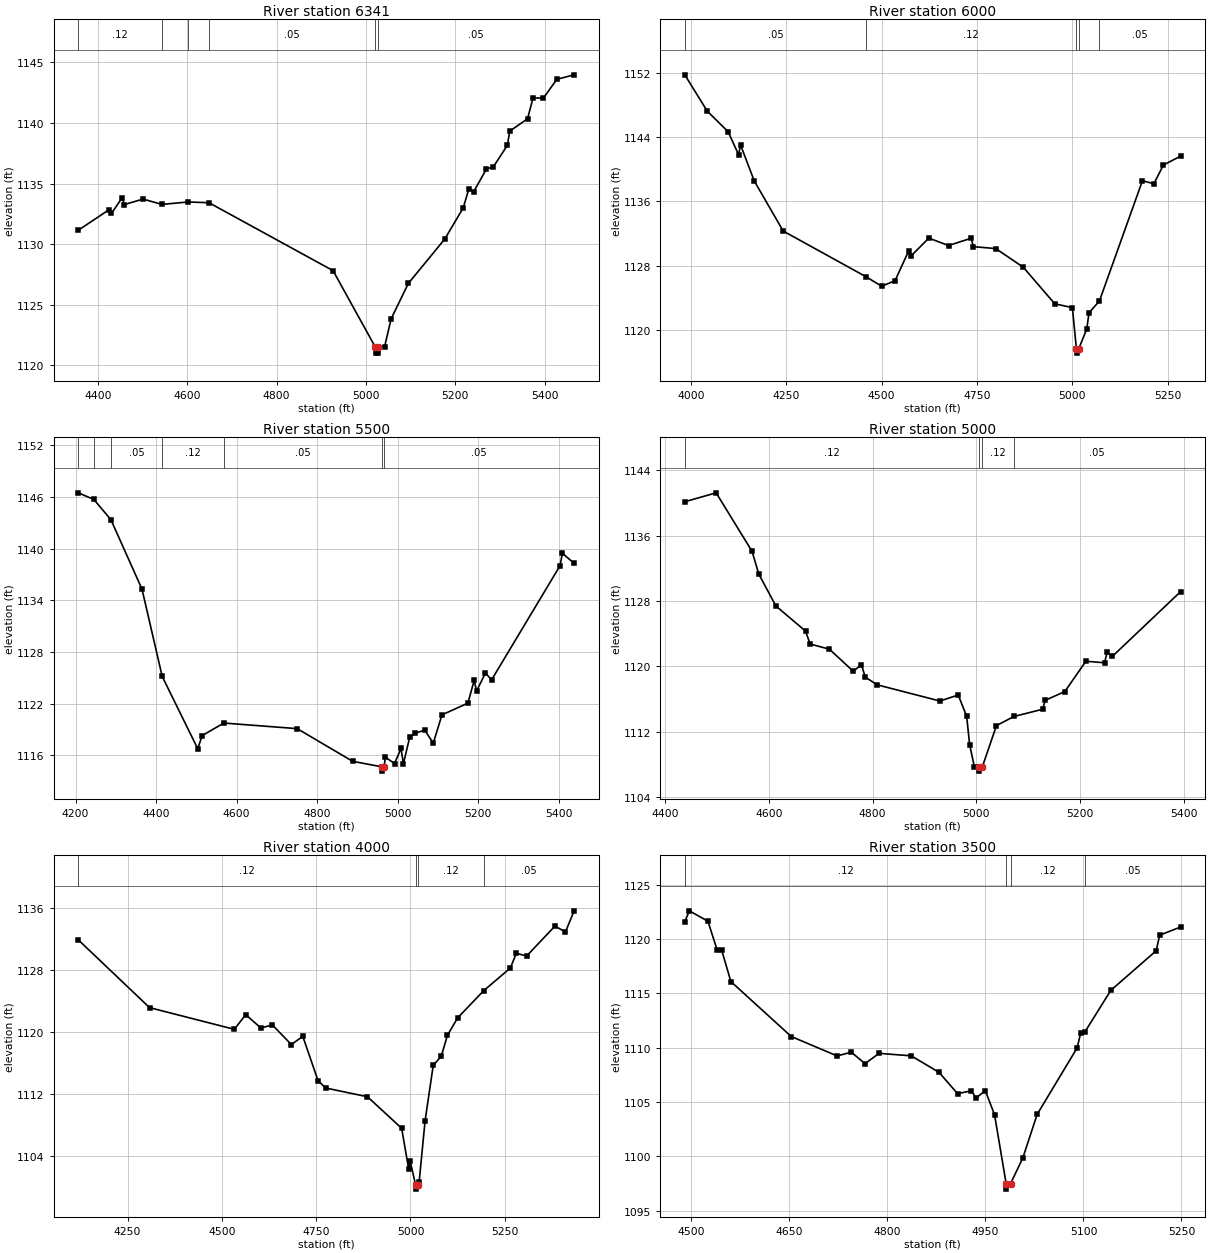
Type RM Length L Ch R = 1 ,6341    ,341,341,341
BEGIN DESCRIPTION:
Mapping XS d7f132e4
END DESCRIPTION:
XS GIS Cut Line= 4
      2820770.87     10217869.72      2821243.05     10218071.09
      2821493.05     10218175.26      2821791.18     10218306.99
#Sta/Elev= 30
  4356.2 1131.15  4424.9 1132.84  4430.3 1132.53    4454 1133.82  4459.4 1133.27
  4501.2 1133.72  4543.3 1133.28  4601.8 1133.48  4648.7 1133.42  4926.5 1127.81
  5021.1  1121.5  5021.6    1121  5026.5    1121  5026.9  1121.5    5042 1121.54
  5056.5 1123.83  5095.1 1126.76  5176.8 1130.43    5218    1133  5230.7 1134.59
  5241.3 1134.33    5270 1136.21  5285.4 1136.38  5316.7 1138.16  5322.1 1139.33
  5361.9 1140.35  5374.2 1142.07  5397.5 1142.06  5427.5 1143.61  5466.3 1143.98
#Mann= 6 ,-1 , 0
  4356.2     .12       0  4543.3     .05       0  4601.8     .12       0
  4648.7     .05       0  5021.1     .05       0  5026.9     .05       0
Bank Sta=5021.1,5026.9
XS Rating Curve= 0 ,0
Exp/Cntr=0.3,0.1

Type RM Length L Ch R = 1 ,6000    ,500,500,500
BEGIN DESCRIPTION:
MULE MT BRANCH 12.0
END DESCRIPTION:
XS GIS Cut Line= 3
      2820405.64      10218203.1      2821390.47     10218452.43
       2821655.7     10218553.12
#Sta/Elev= 30
  3984.1 1151.72  4043.1  1147.2  4097.6 1144.65  4125.1  1141.8  4130.2 1143.01
  4166.1 1138.54    4242 1132.31  4459.1 1126.63  4499.9 1125.46  4535.1 1126.13
    4571 1129.85  4576.1 1129.17  4623.7 1131.43  4675.3 1130.51    4735 1131.42
  4740.1 1130.37  4799.1 1130.13  4871.3 1127.81  4953.8 1123.27    5000 1122.79
  5010.6 1117.64    5011 1117.14  5016.4 1117.64  5037.7 1120.14  5043.6 1122.15
  5070.9 1123.62  5183.6 1138.56  5213.7 1138.19  5238.5 1140.51  5283.7 1141.62
#Mann= 5 ,-1 , 0
  3984.1     .05       0  4459.1     .12       0  5010.6     .07       0
  5016.4     .12       0  5070.9     .05       0
Bank Sta=5010.6,5016.4
XS Rating Curve= 0 ,0
Exp/Cntr=0.3,0.1

Type RM Length L Ch R = 1 ,5500    ,500,500,500
BEGIN DESCRIPTION:
MULE MT BRANCH 11.0
END DESCRIPTION:
XS GIS Cut Line= 3
      2820555.72      10219253.1      2821277.73     10218924.67
      2821655.68     10218703.11
#Sta/Elev= 30
  4206.8 1146.47  4245.3  1145.7  4287.6 1143.36  4364.9 1135.29  4415.1 1125.16
  4503.3 1116.77  4514.4  1118.3  4568.2 1119.75  4750.4  1119.1  4887.9 1115.31
  4960.5 1114.67    4961 1114.17  4966.4 1114.67  4968.9  1115.8    4992 1115.05
  5008.2  1116.8    5014 1115.02  5029.7 1118.11    5044 1118.58  5066.8 1118.93
  5088.3 1117.43  5109.8  1120.7  5174.2 1122.06  5189.9 1124.71  5195.7 1123.46
  5217.9 1125.57  5232.9 1124.75    5403 1138.01  5408.8 1139.45  5438.1 1138.29
#Mann= 7 ,-1 , 0
  4206.8     .05       0  4245.3     .12       0  4287.6     .05       0
  4415.1     .12       0  4568.2     .05       0  4960.5     .05       0
  4966.4     .05       0
Bank Sta=4960.5,4966.4
XS Rating Curve= 0 ,0
Exp/Cntr=0.3,0.1

Type RM Length L Ch R = 1 ,5000    ,1000,1000,1000
BEGIN DESCRIPTION:
MULE MT BRANCH 10.0
END DESCRIPTION:
XS GIS Cut Line= 3
       2820655.7      10219603.1      2821167.28     10219370.44
      2821555.69     10219303.11
#Sta/Elev= 30
    4438 1140.15  4498.4 1141.24  4567.6 1134.09  4580.8 1131.28  4613.7 1127.39
  4670.8 1124.32  4679.7 1122.74  4716.9  1122.1  4763.1 1119.39  4778.5 1120.22
  4786.1 1118.68  4809.2 1117.74    4930 1115.76  4965.3  1116.5  4981.6 1113.88
  4987.3 1110.43  4996.4 1107.72  5005.3 1107.68  5005.8 1107.18  5011.7 1107.68
    5039 1112.75  5072.8 1113.87    5128 1114.75  5133.1 1115.85  5170.9 1116.92
  5211.5 1120.63  5247.4 1120.44  5252.5 1121.71  5262.3 1121.21  5394.2 1129.15
#Mann= 4 ,-1 , 0
    4438     .12       0  5005.3     .07       0  5011.7     .12       0
  5072.8     .05       0
Bank Sta=5005.3,5011.7
XS Rating Curve= 0 ,0
Exp/Cntr=0.3,0.1

Type RM Length L Ch R = 1 ,4000    ,500,500,500
BEGIN DESCRIPTION:
MULE MT BRANCH 8.0
END DESCRIPTION:
XS GIS Cut Line= 3
      2820805.72     10219903.12      2821678.75      10220018.3
      2822055.65     10219803.13
#Sta/Elev= 30
  4119.4 1131.87  4308.2 1123.13  4532.9 1120.33  4563.2 1122.22  4603.5  1120.5
  4633.8  1120.9  4684.2 1118.36  4714.5 1119.43  4754.8 1113.72    4775 1112.76
    4886 1111.63  4976.7 1107.56  4995.2 1102.31  4999.3  1103.3  5013.8 1100.21
  5014.3 1099.71  5020.4 1100.21  5022.9 1100.57  5038.7 1108.51  5060.3 1115.67
  5081.9 1116.88  5097.8 1119.54  5125.1 1121.81  5194.5 1125.33  5264.8 1128.24
  5280.7 1130.14    5308 1129.79  5382.9 1133.64    5411 1132.91    5434 1135.62
#Mann= 4 ,-1 , 0
  4119.4     .12       0  5013.8     .07       0  5020.4     .12       0
  5194.5     .05       0
Bank Sta=5013.8,5020.4
XS Rating Curve= 0 ,0
Exp/Cntr=0.3,0.1

Type RM Length L Ch R = 1 ,3500    ,685,685,685
BEGIN DESCRIPTION:
MULE MT BRANCH 7.0
END DESCRIPTION:
XS GIS Cut Line= 3
      2821355.71     10220003.14      2821703.26     10220376.52
       2821805.7     10220603.15
#Sta/Elev= 30
  4489.9  1121.6  4496.9 1122.59  4525.3 1121.63  4539.4 1118.99  4546.3 1118.98
  4560.4 1116.08  4652.8 1111.02  4723.1 1109.23  4744.7 1109.58  4765.7 1108.52
  4787.2 1109.47  4836.5 1109.24    4879 1107.72  4907.3 1105.76  4928.3 1106.02
  4935.7 1105.37  4949.9 1106.03    4964  1103.8  4981.7 1097.47  4982.2 1096.97
  4988.4 1097.47  5007.2 1099.84  5029.2 1103.86  5090.2 1109.96  5095.7 1111.32
  5102.6 1111.48  5141.9 1115.27  5211.2 1118.91  5216.7 1120.35  5248.7  1121.1
#Mann= 4 ,-1 , 0
  4489.9     .12       0  4981.7     .07       0  4988.4     .12       0
  5102.6     .05       0
Bank Sta=4981.7,4988.4
XS Rating Curve= 0 ,0
Exp/Cntr=0.3,0.1

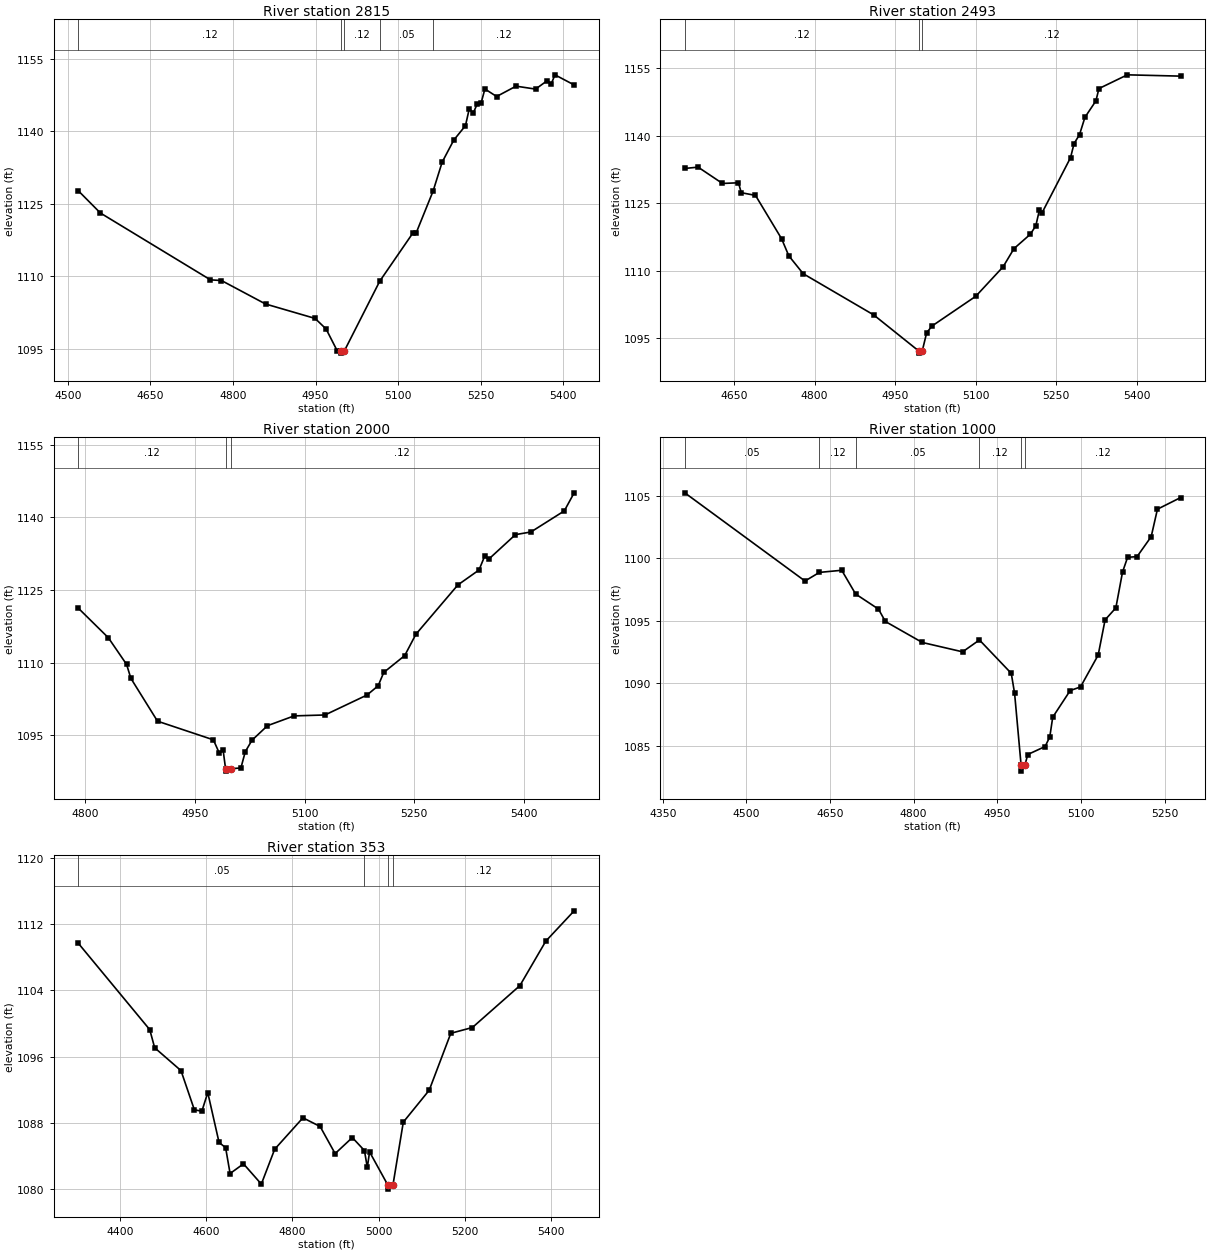
Type RM Length L Ch R = 1 ,2815    ,322,322,322
BEGIN DESCRIPTION:
Mapping XS 853bb09c
END DESCRIPTION:
XS GIS Cut Line= 4
      2821104.16     10220203.04      2821097.22      10220494.7
      2821097.22     10220814.15      2820895.79     10221022.52
#Sta/Elev= 30
    4519 1127.69  4559.1  1123.1  4759.1 1109.29  4779.1 1109.15  4859.2  1104.3
  4949.2 1101.32  4969.2 1099.14  4989.2 1094.68  4995.8 1094.65  4996.3 1094.15
  5002.6 1094.65  5066.7 1109.01  5127.2 1119.01    5133 1119.01  5163.7 1127.64
  5180.1  1133.6  5201.2 1138.16  5222.5 1141.15  5229.5 1144.69  5236.7 1143.77
  5243.6 1145.57  5250.8 1145.79  5257.8 1148.73  5279.1 1147.17  5314.4 1149.31
  5349.9  1148.7    5371 1150.44  5378.2 1149.73  5385.1 1151.65    5420 1149.56
#Mann= 5 ,-1 , 0
    4519     .12       0  4995.8     .07       0  5002.6     .12       0
  5066.7     .05       0  5163.7     .12       0
Bank Sta=4995.8,5002.6
XS Rating Curve= 0 ,0
Exp/Cntr=0.3,0.1

Type RM Length L Ch R = 1 ,2493    ,493,493,493
BEGIN DESCRIPTION:
Mapping XS a17bffb9
END DESCRIPTION:
XS GIS Cut Line= 3
      2820937.49     10220105.83      2820847.22     10220446.09
      2820743.09      10221008.4
#Sta/Elev= 30
  4558.3 1132.71  4583.1    1133  4628.5 1129.38  4658.3 1129.53  4663.5 1127.33
    4690 1126.73  4738.7  1117.1  4752.1 1113.32  4778.9 1109.35  4910.3  1100.2
    4994 1092.22  4994.5 1091.72  5000.8 1092.22    5009 1096.26  5019.2 1097.76
  5100.5 1104.34  5151.4 1110.88  5171.7 1114.92  5202.2 1118.11  5212.4    1120
  5219.1  1123.5  5224.2 1122.91  5277.1 1135.11  5283.6 1138.23  5293.8 1140.21
  5303.9 1144.06  5324.3  1147.7    5330 1150.44  5382.9 1153.49  5482.2  1153.2
#Mann= 3 ,-1 , 0
  4558.3     .12       0    4994     .07       0  5000.8     .12       0
Bank Sta=4994,5000.8
XS Rating Curve= 0 ,0
Exp/Cntr=0.3,0.1

Type RM Length L Ch R = 1 ,2000    ,1000,1000,1000
BEGIN DESCRIPTION:
MULE MT BRANCH 4.0
END DESCRIPTION:
XS GIS Cut Line= 3
      2820305.68      10220253.1      2820353.83      10220457.2
      2820605.67     10220853.09
#Sta/Elev= 30
  4790.3 1121.25  4831.4 1115.15  4856.4 1109.64  4862.2 1106.78  4898.7 1097.93
  4975.2 1094.08  4983.3 1091.35  4988.5 1092.01  4991.9 1088.12  4992.4 1087.62
  4998.7 1088.12  5012.9 1088.27  5018.9 1091.64  5028.1    1094  5049.3    1097
  5085.7 1099.02    5128 1099.21  5185.6 1103.33  5200.8 1105.23  5208.5 1107.99
  5237.2 1111.47  5252.5 1115.87    5310 1126.05  5338.9 1129.13  5346.5 1131.92
  5352.4 1131.39  5388.8 1136.43    5410 1136.98  5455.7 1141.33  5469.2 1145.06
#Mann= 3 ,-1 , 0
  4790.3     .12       0  4991.9     .07       0  4998.7     .12       0
Bank Sta=4991.9,4998.7
XS Rating Curve= 0 ,0
Exp/Cntr=0.3,0.1

Type RM Length L Ch R = 1 ,1000    ,647,647,647
BEGIN DESCRIPTION:
MULE MT BRANCH 2.0
END DESCRIPTION:
XS GIS Cut Line= 3
      2819505.69     10220503.13      2819841.77     10221012.79
      2820105.65      10221103.1
#Sta/Elev= 30
  4389.5 1105.23  4605.1 1098.17    4631 1098.86    4671 1099.03  4695.9 1097.13
  4736.9 1095.92  4749.3 1094.93  4815.5 1093.25  4887.8  1092.5    4918 1093.45
  4975.1 1090.78  4981.1 1089.17  4992.7 1083.45  4993.2 1082.95  4999.7 1083.45
  5004.7 1084.28  5035.8 1084.92  5044.2 1085.69  5049.5 1087.27  5080.8  1089.4
  5099.3 1089.69    5131 1092.24  5143.4 1095.06  5162.7 1096.02  5174.7 1098.89
  5183.8 1100.07  5200.7 1100.12  5226.1 1101.72  5237.3 1103.92  5278.9 1104.85
#Mann= 6 ,-1 , 0
  4389.5     .05       0    4631     .12       0  4695.9     .05       0
    4918     .12       0  4992.7     .07       0  4999.7     .12       0
Bank Sta=4992.7,4999.7
XS Rating Curve= 0 ,0
Exp/Cntr=0.3,0.1

Type RM Length L Ch R = 1 ,353     ,0,0,0
BEGIN DESCRIPTION:
MULE MT BRANCH 1.0
END DESCRIPTION:
XS GIS Cut Line= 3
      2819005.71     10221753.11      2819678.25       10221572.
      2820131.36     10221598.84
#Sta/Elev= 30
  4303.5  1109.7  4469.2 1099.25  4480.6 1097.06  4541.7 1094.29  4572.7 1089.55
  4590.1 1089.38  4603.8 1091.63    4630  1085.6  4645.2 1084.97  4655.6 1081.84
  4686.7 1083.01  4728.1 1080.56  4759.1 1084.78  4824.6 1088.58  4864.5 1087.53
  4899.3 1084.25  4939.2 1086.19  4967.3 1084.62    4974 1082.57  4979.2 1084.46
  5021.5 1080.45    5022 1079.95  5033.5 1080.45  5057.5 1088.06  5117.6 1091.92
  5167.7 1098.81  5217.8 1099.51    5328 1104.58  5388.1 1109.96  5453.9 1113.63
#Mann= 4 ,-1 , 0
  4303.5     .05       0  4967.3     .12       0  5021.5     .07       0
  5033.5     .12       0
Bank Sta=5021.5,5033.5
XS Rating Curve= 0 ,0
Exp/Cntr=0.3,0.1

Chan Stop Cuts=-1
Use User Specified Reach Order=0
Composite Channel Slope=5