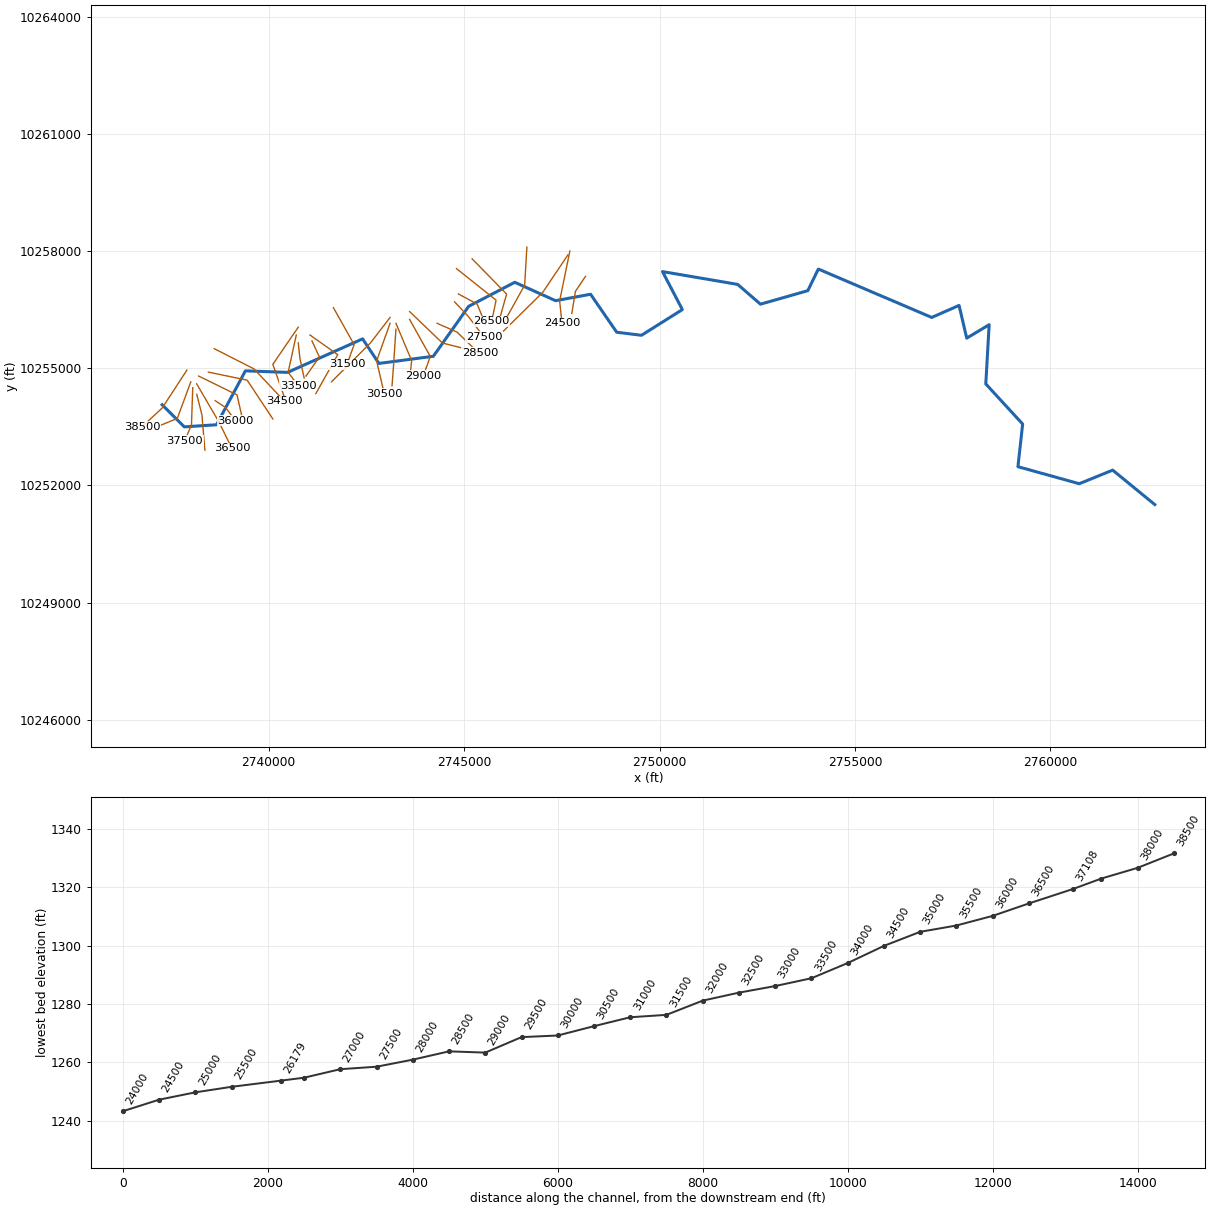
--- NORTH WILLOW CREEK.prj (project) ---

Proj Title=NORTH WILLOW CREEK Base Level Engineering
Current Plan=p01
Default Exp/Contr=0.3,0.1
English Units
Geom File=g01
Flow File=f01
Plan File=p01
Y Axis Title=Elevation
X Axis Title(PF)=Main Channel Distance
X Axis Title(XS)=Station
BEGIN DESCRIPTION:
NORTH WILLOW CREEK
END DESCRIPTION:
DSS Export Rating Curves= 0
DSS Export Rating Curve Sorted= 0
DSS Export Volume Flow Curves= 0
DXF OffsetX= 0
DXF OffsetY= 0
DXF ScaleX= 1
DXF ScaleY= 10

--- NORTH WILLOW CREEK.p01 (plan) ---

Plan Title=Multiple Run
Short Identifier=Multiple
Geom File=g01
Flow File=f01
Subcritical Flow
K Sum by GR= 0
Std Step Tol= 0.01
Critical Tol= 0.01
Num of Std Step Trials= 20
Max Error Tol= 0.3
Flow Tol Ratio= 0.001
Split Flow NTrial= 30
Split Flow Tol= 0.02
Split Flow Ratio= 0.02
Log Output Level= 0
Friction Slope Method= 1
Unsteady Friction Slope Method= 2
Unsteady Bridges Friction Slope Method= 1
Parabolic Critical Depth
Global Vel Dist=  1 , 1 , 1
Global Log Level= 0
CheckData=True
Encroach Param= -1, 0, 0, 0
BEGIN DESCRIPTION:
Multiple Run
END DESCRIPTION:

--- NORTH WILLOW CREEK.f01 (steady flow) ---

Flow Title=Multiple
Program Version=4.10
Number of Profiles= 7
Profile Names=10-year,25-year,50-year,1pct_min,100-year,1pct_plu,500-year
River Rch & RM=NORTH WILLOW CRE,Reach-1         ,38500
     267     420     500     346     651    1223     893
River Rch & RM=NORTH WILLOW CRE,Reach-1         ,36500
     533     873    1162     744    1554    3246    2124
River Rch & RM=NORTH WILLOW CRE,Reach-1         ,33000
     760    1277    1667     981    2250    5160    3063
River Rch & RM=NORTH WILLOW CRE,Reach-1         ,28000
     903    1535    1991    1234    2700    5907    3666
River Rch & RM=NORTH WILLOW CRE,Reach-1         ,25500
    1429    2501    3324    2402    4576    8718    6185
River Rch & RM=NORTH WILLOW CRE,Reach-1         ,18000
    1712    3039    4071    3248    5648    9821    7646
River Rch & RM=NORTH WILLOW CRE,Reach-1         ,12500
    2258    4084    5517    4358    7726   13695   10446
River Rch & RM=NORTH WILLOW CRE,Reach-1         ,4000
    2820    5206    7522    5777   10670   19708   14357
Boundary for River Rch & Prof#=NORTH WILLOW CRE,Reach-1         , 1
Up Type= 0
Dn Type= 3
Dn Slope=0.001
Boundary for River Rch & Prof#=NORTH WILLOW CRE,Reach-1         , 2
Up Type= 0
Dn Type= 3
Dn Slope=0.001
Boundary for River Rch & Prof#=NORTH WILLOW CRE,Reach-1         , 3
Up Type= 0
Dn Type= 3
Dn Slope=0.001
Boundary for River Rch & Prof#=NORTH WILLOW CRE,Reach-1         , 4
Up Type= 0
Dn Type= 3
Dn Slope=0.001
Boundary for River Rch & Prof#=NORTH WILLOW CRE,Reach-1         , 5
Up Type= 0
Dn Type= 3
Dn Slope=0.001
Boundary for River Rch & Prof#=NORTH WILLOW CRE,Reach-1         , 6
Up Type= 0
Dn Type= 3
Dn Slope=0.001
Boundary for River Rch & Prof#=NORTH WILLOW CRE,Reach-1         , 7
Up Type= 0
Dn Type= 3
Dn Slope=0.001
DSS Import GetInterval= 0
DSS Import GetPeak= 0
DSS Import FillOption= 0

--- NORTH WILLOW CREEK.g01 (geometry) ---

Geom Title=Existing Conditions

River Reach=NORTH WILLOW CRE,Reach-1
Reach XY= 30
      2737273.00     10254067.00      2737840.00     10253501.00
      2738664.25     10253555.00      2739403.25     10254935.00
      2740482.75     10254896.00      2742402.25     10255754.00
      2742820.25     10255125.00      2744213.25     10255309.00
      2745117.00     10256588.00      2746297.00     10257203.00
      2747340.00     10256732.00      2748235.75     10256897.00
      2748905.00     10255924.00      2749538.75     10255846.00
      2750584.75     10256504.00      2750076.50     10257477.00
      2752000.50     10257149.00      2752583.75     10256642.00
      2753794.75     10256988.00      2754064.00     10257542.00
      2756965.75     10256303.00      2757665.25     10256611.00
      2757861.25     10255773.00      2758435.25     10256117.00
      2758349.00     10254601.00      2759292.25     10253573.00
      2759171.75     10252481.00      2760742.00     10252045.00
      2761596.00     10252393.00      2762673.25     10251511.00

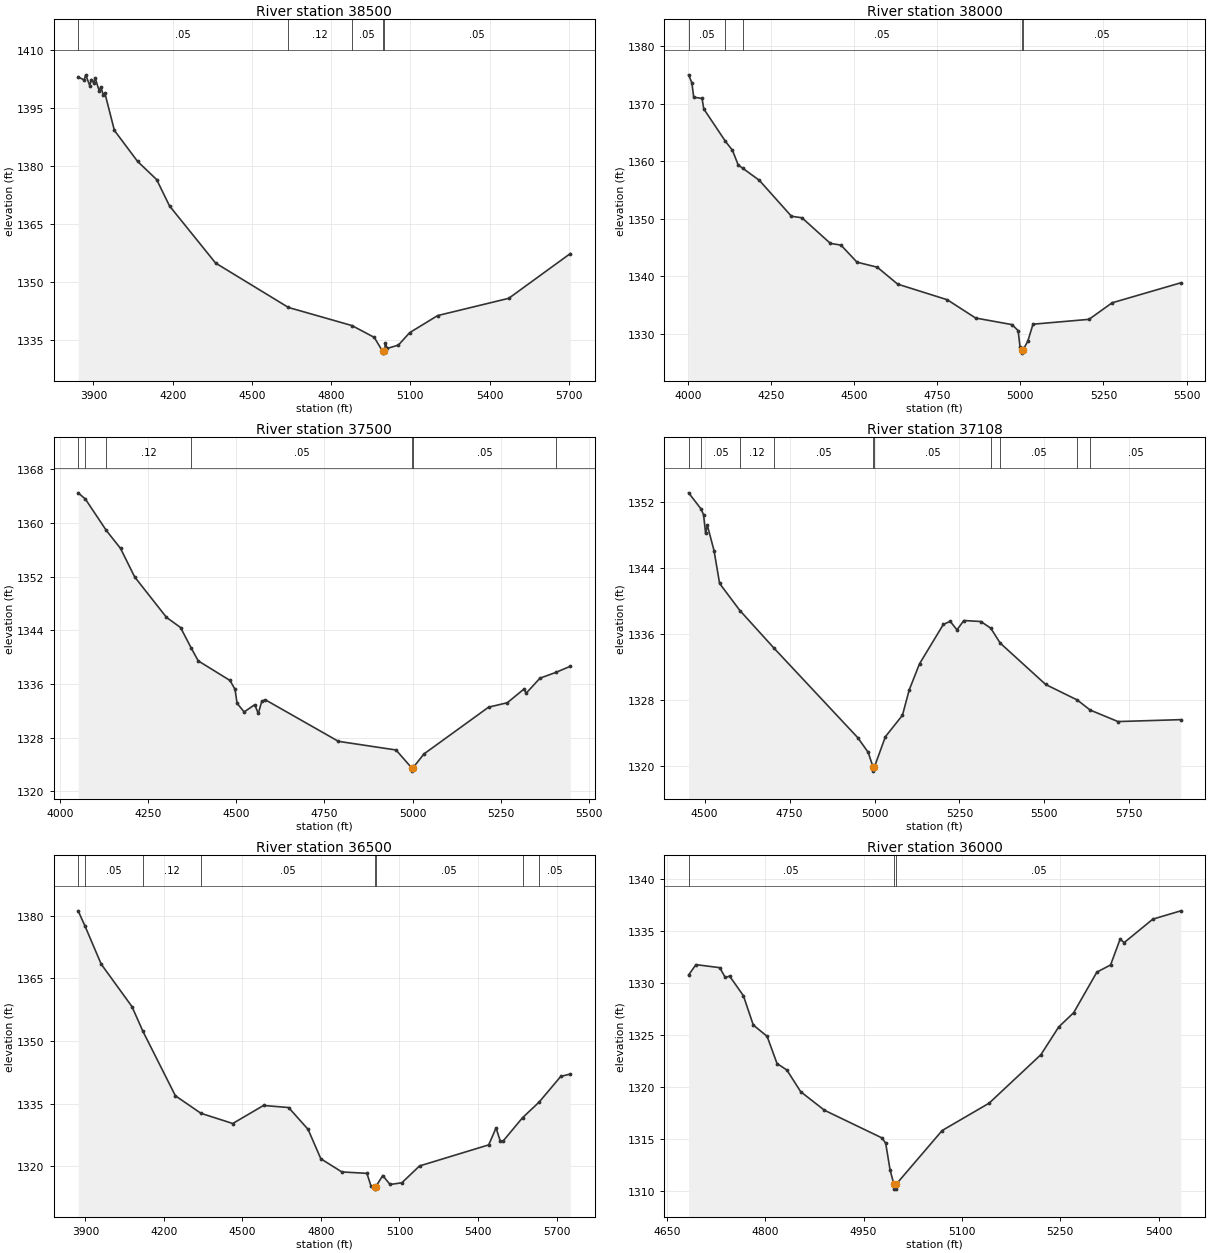
Type RM Length L Ch R = 1,38500,500,500,500
BEGIN DESCRIPTION:
NORTH WILLOW CREEK 77.0
END DESCRIPTION:
XS GIS Cut Line= 3
      2737905.69     10254953.12      2737273.71     10253982.78
      2736755.68     10253503.11
#Sta/Elev= 30
  3842.0 1403.00  3864.7 1402.22  3870.7 1403.55  3885.8 1400.78  3891.8 1402.33
  3900.9 1401.51  3906.9 1402.66  3922.0 1399.33  3928.0 1400.47  3937.2 1398.32
  3943.1 1398.85  3979.3 1389.18  4066.9 1381.20  4139.4 1376.48  4188.1 1369.67
  4362.7 1354.91  4638.4 1343.45  4879.0 1338.77  4963.4 1335.72  4994.8 1332.15
  4995.1 1331.65  4998.8 1332.15  5002.1 1332.15  5005.5 1334.29  5012.3 1332.86
  5054.8 1333.73  5097.4 1336.93  5203.4 1341.35  5472.7 1345.81  5706.0 1357.38
#Mann=5,-1,0
  3842.0    0.05       0  4638.4    0.12       0  4879.0    0.05       0
  4994.8    0.05       0  4998.8    0.05       0
Bank Sta=4994.8,4998.8
Exp/Cntr=0.3,0.1

Type RM Length L Ch R = 1,38000,500,500,500
BEGIN DESCRIPTION:
NORTH WILLOW CREEK 76.0
END DESCRIPTION:
XS GIS Cut Line= 3
      2738005.69     10254653.13      2737661.13     10253717.03
      2737214.68     10253533.24
#Sta/Elev= 30
  4002.5 1374.98  4012.4 1373.58  4017.8 1371.10  4042.9 1370.88  4048.2 1369.06
  4113.3 1363.44  4134.3 1361.89  4151.7 1359.34  4165.1 1358.78  4215.0 1356.69
  4311.7 1350.45  4343.5 1350.18  4428.8 1345.74  4460.7 1345.44  4508.9 1342.48
  4569.8 1341.61  4631.2 1338.67  4780.4 1335.96  4865.7 1332.79  4974.9 1331.65
  4993.5 1330.62  4999.4 1327.72  5003.9 1327.20  5004.1 1326.70  5007.9 1327.20
  5022.8 1328.81  5038.3 1331.72  5206.6 1332.56  5276.2 1335.43  5482.8 1338.90
#Mann=5,-1,0
  4002.5    0.05       0  4113.3    0.12       0  4165.1    0.05       0
  5003.9    0.05       0  5007.9    0.05       0
Bank Sta=5003.9,5007.9
Exp/Cntr=0.3,0.1

Type RM Length L Ch R = 1,37500,392,392,392
BEGIN DESCRIPTION:
NORTH WILLOW CREEK 75.0
END DESCRIPTION:
XS GIS Cut Line= 3
      2738055.68     10254503.08      2738023.63     10253555.92
      2737851.83     10253143.69
#Sta/Elev= 30
  4052.3 1364.50  4072.7 1363.58  4132.0 1358.90  4172.3 1356.22  4212.4 1351.97
  4302.4 1345.95  4342.4 1344.43  4373.0 1341.33  4392.5 1339.46  4482.5 1336.54
  4496.7 1335.22  4502.5 1333.14  4522.5 1331.85  4552.6 1332.93  4562.6 1331.62
  4572.6 1333.46  4582.6 1333.66  4789.6 1327.47  4952.8 1326.18  4996.9 1323.53
  4997.2 1323.03  5000.9 1323.53  5031.9 1325.59  5215.0 1332.56  5268.0 1333.22
  5315.7 1335.28  5321.1 1334.62  5360.6 1336.88  5406.0 1337.75  5446.6 1338.66
#Mann=7,-1,0
  4052.3    0.12       0  4072.7    0.05       0  4132.0    0.12       0
  4373.0    0.05       0  4996.9    0.05       0  5000.9    0.05       0
  5406.0    0.12       0
Bank Sta=4996.9,5000.9
Exp/Cntr=0.3,0.1

Type RM Length L Ch R = 1,37108,608,608,608
BEGIN DESCRIPTION:
NORTH WILLOW CREEK 74.0
END DESCRIPTION:
XS GIS Cut Line= 3
      2738158.34     10254335.67      2738291.00     10253805.00
      2738366.41     10252906.86
#Sta/Elev= 30
  4453.0 1353.07  4489.2 1351.14  4496.9 1350.44  4503.0 1348.16  4508.1 1349.15
  4527.8 1346.09  4544.2 1342.12  4604.1 1338.84  4704.3 1334.30  4950.4 1323.50
  4981.3 1321.72  4995.7 1319.94  4996.0 1319.44  4999.7 1319.94  5032.0 1323.60
  5082.2 1326.19  5102.2 1329.26  5132.4 1332.41  5202.6 1337.17  5222.7 1337.54
  5242.7 1336.51  5262.8 1337.64  5313.0 1337.52  5342.2 1336.71  5369.9 1334.91
  5503.7 1329.91  5596.9 1328.03  5634.6 1326.82  5716.4 1325.43  5901.3 1325.66
#Mann=10,-1,0
  4453.0    0.12       0  4489.2    0.05       0  4604.1    0.12       0
  4704.3    0.05       0  4995.7    0.03       0  4999.7    0.05       0
  5342.2    0.12       0  5369.9    0.05       0  5596.9    0.12       0
  5634.6    0.05       0
Bank Sta=4995.7,4999.7
Exp/Cntr=0.3,0.1

Type RM Length L Ch R = 1,36500,500,500,500
BEGIN DESCRIPTION:
NORTH WILLOW CREEK 73.0
END DESCRIPTION:
XS GIS Cut Line= 3
      2738155.71     10254603.07      2738724.14     10253629.00
      2739055.67     10252953.13
#Sta/Elev= 30
  3872.2 1381.16  3897.8 1377.60  3960.2 1368.40  4077.6 1358.24  4119.7 1352.30
  4243.8 1336.85  4341.6 1332.65  4462.9 1330.21  4580.4 1334.53  4676.3 1334.04
  4750.7 1328.81  4799.5 1321.76  4879.7 1318.61  4975.6 1318.27  4991.3 1315.19
  5004.6 1314.99  5004.8 1314.49  5008.6 1314.99  5036.0 1317.75  5064.0 1315.60
  5109.0 1316.01  5176.5 1320.04  5440.8 1325.09  5468.9 1329.15  5485.5 1325.93
  5497.0 1326.09  5570.1 1331.60  5633.1 1335.31  5716.3 1341.50  5752.8 1342.06
#Mann=8,-1,0
  3872.2    0.12       0  3897.8    0.05       0  4119.7    0.12       0
  4341.6    0.05       0  5004.6    0.05       0  5008.6    0.05       0
  5570.1    0.12       0  5633.1    0.05       0
Bank Sta=5004.6,5008.6
Exp/Cntr=0.3,0.1

Type RM Length L Ch R = 1,36000,500,500,500
BEGIN DESCRIPTION:
NORTH WILLOW CREEK 72.0
END DESCRIPTION:
XS GIS Cut Line= 3
      2738628.99     10254172.76      2738893.65     10253998.82
      2739155.69     10253653.11
#Sta/Elev= 30
  4683.3 1330.80  4694.5 1331.79  4730.7 1331.50  4739.2 1330.56  4745.8 1330.69
  4766.8 1328.81  4781.9 1325.99  4803.0 1324.90  4818.1 1322.29  4833.2 1321.66
  4854.2 1319.58  4890.4 1317.80  4977.8 1315.15  4983.8 1314.64  4990.5 1312.06
  4996.2 1310.72  4996.5 1310.22  5000.0 1310.22  5000.2 1310.72  5069.9 1315.85
  5141.5 1318.48  5220.5 1323.14  5247.6 1325.80  5270.5 1327.18  5305.8 1331.07
  5326.7 1331.76  5341.2 1334.23  5347.5 1333.91  5391.1 1336.16  5433.8 1336.96
#Mann=3,-1,0
  4683.3    0.05       0  4996.2    0.03       0  5000.2    0.05       0
Bank Sta=4996.2,5000.2
Exp/Cntr=0.3,0.1

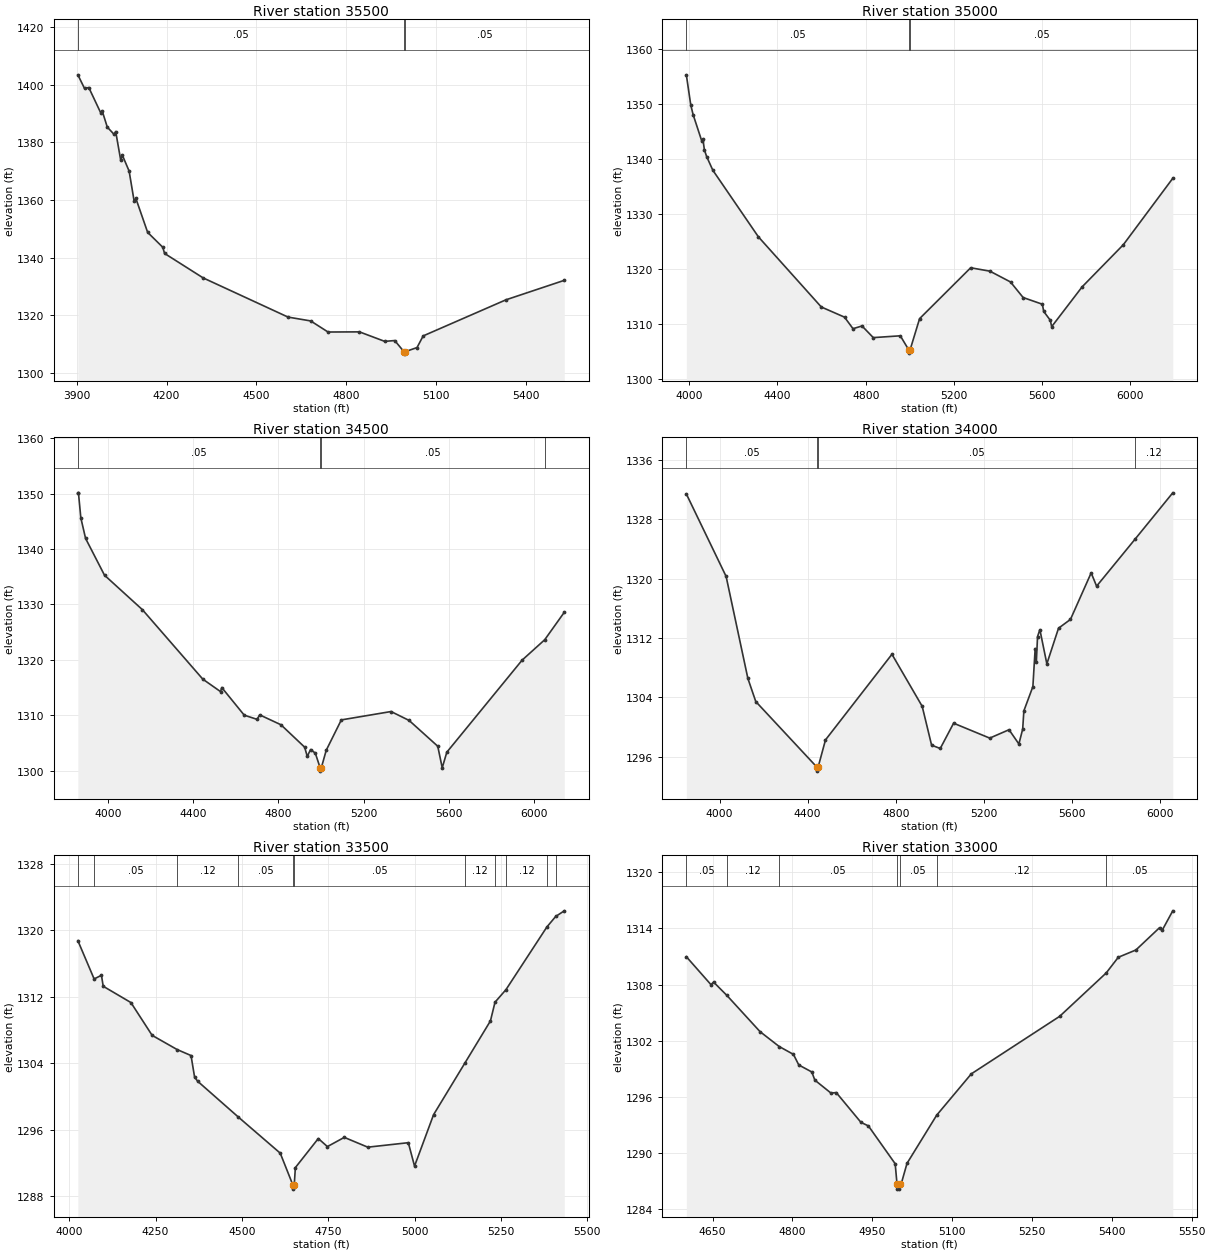
Type RM Length L Ch R = 1,35500,500,500,500
BEGIN DESCRIPTION:
NORTH WILLOW CREEK 71.0
END DESCRIPTION:
XS GIS Cut Line= 3
      2738205.67     10254803.12      2739189.51     10254319.00
      2739305.68     10253803.12
#Sta/Elev= 30
  3903.5 1403.42  3925.8 1398.69  3940.0 1399.02  3979.4 1390.35  3984.9 1390.88
  4001.8 1385.29  4024.3 1382.80  4029.9 1383.76  4046.8 1373.76  4052.4 1375.50
  4074.8 1370.04  4091.7 1359.52  4097.3 1360.56  4136.7 1348.79  4187.2 1343.63
  4193.3 1341.48  4322.0 1333.01  4605.7 1319.42  4681.5 1318.08  4739.4 1314.24
  4844.4 1314.29  4928.7 1311.00  4962.3 1311.28  4993.1 1307.42  4993.3 1306.92
  4997.1 1307.42  5036.8 1308.85  5057.3 1312.89  5334.0 1325.41  5528.8 1332.16
#Mann=3,-1,0
  3903.5    0.05       0  4993.1    0.03       0  4997.1    0.05       0
Bank Sta=4993.1,4997.1
Exp/Cntr=0.3,0.1

Type RM Length L Ch R = 1,35000,500,500,500
BEGIN DESCRIPTION:
NORTH WILLOW CREEK 70.0
END DESCRIPTION:
XS GIS Cut Line= 3
      2738455.70     10254903.11      2739447.83     10254697.55
      2740105.66     10253703.14
#Sta/Elev= 30
  3986.8 1355.35  4006.8 1349.88  4017.4 1348.13  4056.9 1343.30  4062.0 1343.66
  4068.5 1341.74  4078.7 1340.50  4107.1 1337.99  4313.6 1325.89  4598.7 1313.14
  4704.1 1311.29  4742.5 1309.19  4783.3 1309.69  4834.4 1307.57  4957.0 1307.90
  4996.6 1305.25  4996.9 1304.75  5000.6 1305.25  5044.4 1311.02  5276.1 1320.27
  5363.3 1319.65  5456.6 1317.69  5513.8 1314.86  5601.1 1313.64  5607.1 1312.34
  5637.2 1310.71  5643.2 1309.56  5781.6 1316.81  5968.2 1324.46  6192.3 1336.53
#Mann=3,-1,0
  3986.8    0.05       0  4996.6    0.05       0  5000.6    0.05       0
Bank Sta=4996.6,5000.6
Exp/Cntr=0.3,0.1

Type RM Length L Ch R = 1,34500,500,500,500
BEGIN DESCRIPTION:
NORTH WILLOW CREEK 69.0
END DESCRIPTION:
XS GIS Cut Line= 3
      2738605.70     10255503.10      2739623.56     10254985.29
      2740405.66     10254153.14
#Sta/Elev= 30
  3858.0 1350.13  3860.8 1350.13  3871.9 1345.62  3894.2 1341.91  3983.1 1335.27
  4161.1 1329.05  4444.7 1316.52  4528.1 1314.27  4533.7 1315.01  4639.3 1310.02
  4699.5 1309.27  4711.7 1310.08  4811.7 1308.29  4922.9 1304.25  4935.1 1302.59
  4950.8 1303.83  4973.0 1303.17  4996.4 1300.43  4996.6 1299.93  5000.4 1300.43
  5024.3 1303.70  5095.1 1309.17  5328.6 1310.68  5413.5 1309.07  5547.9 1304.42
  5568.9 1300.53  5590.4 1303.34  5944.0 1319.95  6050.2 1323.63  6142.0 1328.58
#Mann=4,-1,0
  3858.0    0.05       0  4996.4    0.05       0  5000.4    0.05       0
  6050.2    0.12       0
Bank Sta=4996.4,5000.4
Exp/Cntr=0.3,0.1

Type RM Length L Ch R = 1,34000,500,500,500
BEGIN DESCRIPTION:
NORTH WILLOW CREEK 68.0
END DESCRIPTION:
XS GIS Cut Line= 3
      2740755.66     10256053.08      2740105.55     10255102.77
      2740455.68     10254103.11
#Sta/Elev= 30
  3848.6 1331.40  4029.4 1320.28  4128.2 1306.54  4164.1 1303.42  4443.1 1294.54
  4443.3 1294.04  4447.1 1294.54  4481.0 1298.25  4783.0 1309.79  4920.4 1302.78
  4963.2 1297.54  5002.5 1297.09  5063.2 1300.50  5227.4 1298.49  5315.1 1299.62
  5359.9 1297.70  5377.2 1299.71  5382.5 1302.16  5423.5 1305.43  5433.9 1310.56
  5439.2 1308.73  5444.7 1312.18  5455.3 1313.11  5487.0 1308.50  5540.0 1313.30
  5594.3 1314.49  5688.4 1320.76  5713.1 1318.97  5888.6 1325.33  6059.2 1331.55
#Mann=4,-1,0
  3848.6    0.05       0  4443.1    0.03       0  4447.1    0.05       0
  5888.6    0.12       0
Bank Sta=4443.1,4447.1
Exp/Cntr=0.3,0.1

Type RM Length L Ch R = 1,33500,500,500,500
BEGIN DESCRIPTION:
NORTH WILLOW CREEK 67.0
END DESCRIPTION:
XS GIS Cut Line= 3
      2740705.69     10255853.15      2740496.76     10254900.90
      2740755.69     10254553.10
#Sta/Elev= 30
  4025.1 1318.74  4072.2 1314.13  4093.4 1314.57  4098.5 1313.25  4178.7 1311.29
  4240.2 1307.34  4312.6 1305.63  4352.8 1304.91  4363.0 1302.34  4371.6 1301.83
  4490.2 1297.49  4611.1 1293.16  4647.7 1289.33  4647.9 1288.83  4651.7 1289.33
  4654.9 1291.42  4721.3 1294.92  4747.7 1293.95  4796.6 1295.06  4864.6 1293.88
  4982.0 1294.42  5000.0 1291.60  5055.1 1297.79  5146.0 1304.02  5219.8 1309.08
  5233.0 1311.33  5264.7 1312.84  5383.3 1320.39  5408.7 1321.65  5433.6 1322.33
#Mann=11,-1,0
  4025.1    0.12       0  4072.2    0.05       0  4312.6    0.12       0
  4490.2    0.05       0  4647.7    0.05       0  4651.7    0.05       0
  5146.0    0.12       0  5233.0    0.05       0  5264.7    0.12       0
  5383.3    0.05       0  5408.7    0.12       0
Bank Sta=4647.7,4651.7
Exp/Cntr=0.3,0.1

Type RM Length L Ch R = 1,33000,500,500,500
BEGIN DESCRIPTION:
NORTH WILLOW CREEK 66.0
END DESCRIPTION:
XS GIS Cut Line= 3
      2740755.68     10255653.14      2740798.14     10255256.21
      2740905.69     10254753.07
#Sta/Elev= 30
  4600.8 1310.97  4647.0 1307.99  4652.0 1308.26  4676.9 1306.84  4739.2 1302.97
  4775.2 1301.38  4802.0 1300.54  4812.0 1299.41  4836.5 1298.66  4842.2 1297.79
  4872.4 1296.41  4882.4 1296.46  4928.8 1293.28  4942.8 1292.90  4993.1 1288.86
  4996.6 1286.65  4997.0 1286.15  5001.1 1286.15  5001.5 1286.65  5004.1 1286.65
  5015.3 1288.90  5071.1 1294.05  5136.1 1298.46  5302.0 1304.60  5389.4 1309.23
  5412.2 1310.91  5445.3 1311.69  5489.7 1314.07  5494.8 1313.81  5514.5 1315.87
#Mann=7,-1,0
  4600.8    0.05       0  4676.9    0.12       0  4775.2    0.05       0
  4996.6    0.03       0  5001.5    0.05       0  5071.1    0.12       0
  5389.4    0.05       0
Bank Sta=4996.6,5001.5
Exp/Cntr=0.3,0.1

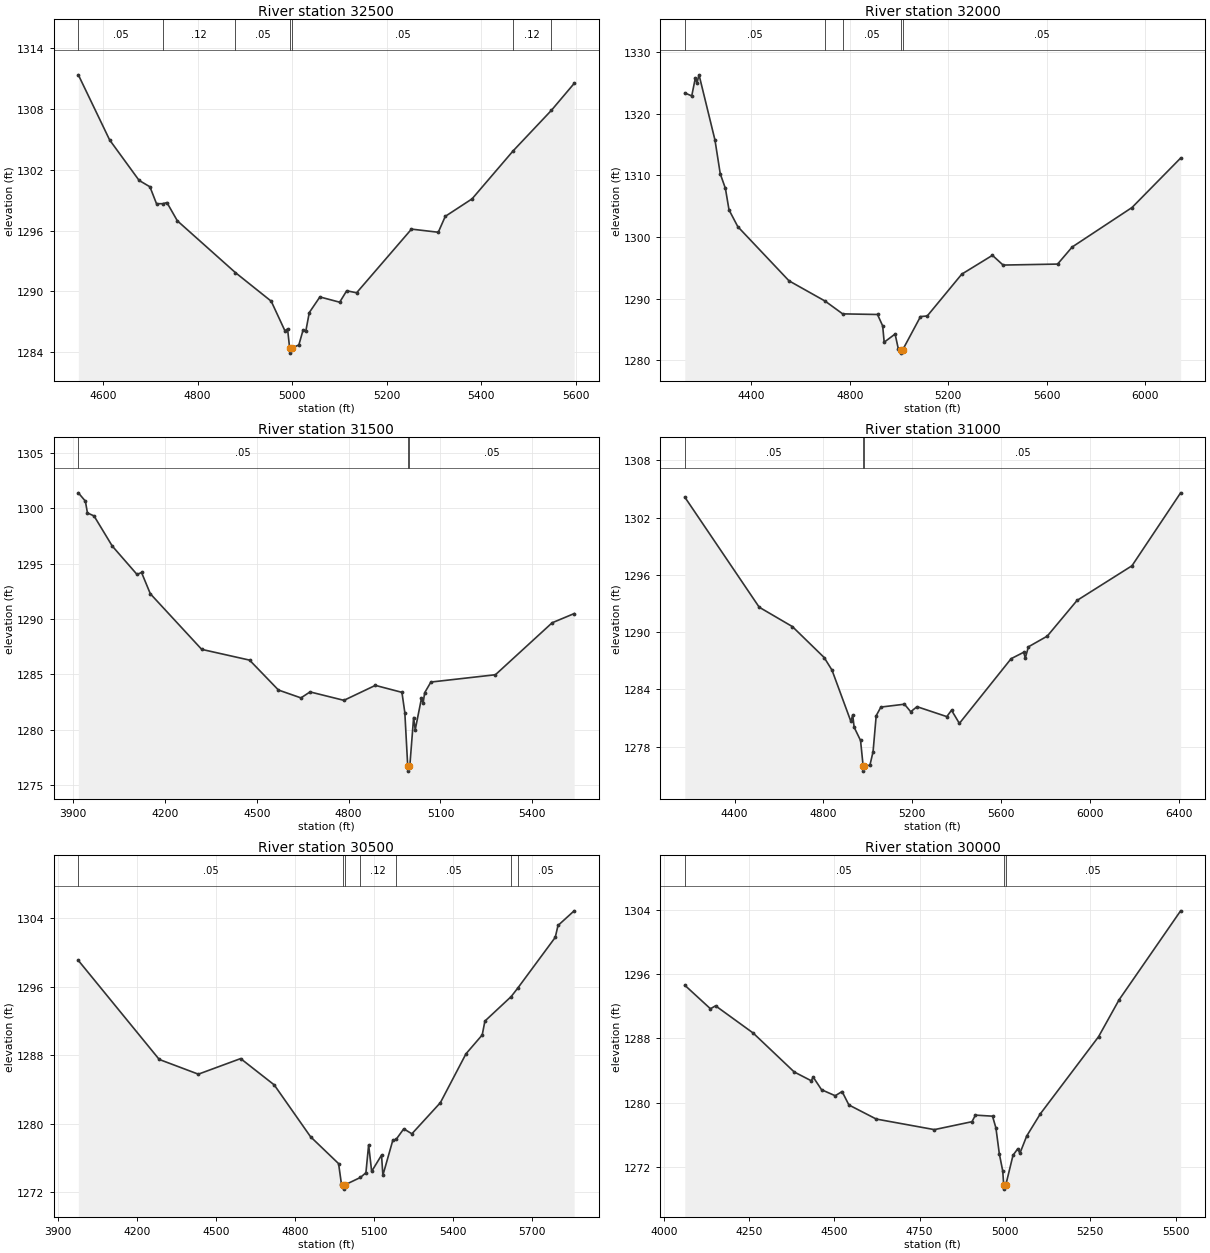
Type RM Length L Ch R = 1,32500,500,500,500
BEGIN DESCRIPTION:
NORTH WILLOW CREEK 65.0
END DESCRIPTION:
XS GIS Cut Line= 3
      2741105.69     10255703.11      2741296.53     10255292.82
      2740955.71     10254803.15
#Sta/Elev= 30
  4547.5 1311.38  4613.7 1304.95  4676.1 1300.95  4699.0 1300.32  4712.9 1298.65
  4726.2 1298.65  4735.0 1298.76  4757.0 1296.96  4879.7 1291.85  4955.6 1289.02
  4984.6 1286.10  4990.2 1286.28  4994.6 1284.39  4995.0 1283.89  4999.5 1284.39
  5014.1 1284.70  5022.8 1286.13  5028.9 1286.09  5036.2 1287.90  5058.6 1289.44
  5100.5 1288.92  5115.3 1290.05  5136.3 1289.85  5252.4 1296.14  5309.1 1295.83
  5323.9 1297.40  5380.6 1299.13  5467.3 1303.86  5548.6 1307.88  5596.6 1310.53
#Mann=7,-1,0
  4547.5    0.05       0  4726.2    0.12       0  4879.7    0.05       0
  4994.6    0.03       0  4999.5    0.05       0  5467.3    0.12       0
  5548.6    0.05       0
Bank Sta=4994.6,4999.5
Exp/Cntr=0.3,0.1

Type RM Length L Ch R = 1,32000,500,500,500
BEGIN DESCRIPTION:
NORTH WILLOW CREEK 64.0
END DESCRIPTION:
XS GIS Cut Line= 3
      2741055.72     10255853.09      2741765.63     10255350.33
      2741205.67     10254353.09
#Sta/Elev= 30
  4130.1 1323.37  4158.3 1322.89  4173.1 1325.83  4179.3 1324.96  4187.9 1326.31
  4252.6 1315.73  4274.1 1310.25  4295.0 1307.88  4309.7 1304.39  4345.4 1301.67
  4553.4 1292.88  4699.7 1289.60  4771.3 1287.52  4912.7 1287.42  4933.7 1285.57
  4939.8 1282.92  4984.1 1284.25  4997.0 1281.89  5009.6 1281.65  5010.0 1281.15
  5014.5 1281.65  5087.3 1287.08  5114.7 1287.18  5255.0 1293.97  5379.4 1297.02
  5422.7 1295.44  5644.0 1295.60  5703.3 1298.37  5946.3 1304.78  6143.7 1312.80
#Mann=5,-1,0
  4130.1    0.05       0  4699.7    0.12       0  4771.3    0.05       0
  5009.6    0.03       0  5014.5    0.05       0
Bank Sta=5009.6,5014.5
Exp/Cntr=0.3,0.1

Type RM Length L Ch R = 1,31500,500,500,500
BEGIN DESCRIPTION:
NORTH WILLOW CREEK 63.0
END DESCRIPTION:
XS GIS Cut Line= 3
      2741655.67     10256553.13      2742185.11     10255608.82
      2742005.68     10255103.11
#Sta/Elev= 30
  3917.4 1301.39  3940.4 1300.64  3947.1 1299.58  3968.8 1299.30  4028.1 1296.59
  4109.1 1294.02  4123.8 1294.20  4152.5 1292.28  4320.3 1287.26  4476.6 1286.29
  4570.9 1283.59  4644.4 1282.88  4674.1 1283.42  4784.7 1282.66  4887.4 1284.01
  4974.2 1283.38  4983.6 1281.56  4993.0 1276.77  4993.4 1276.27  4998.0 1276.77
  5000.0 1276.77  5012.3 1281.11  5017.6 1280.01  5037.9 1282.83  5043.2 1282.39
  5048.5 1283.35  5068.7 1284.31  5279.5 1284.97  5464.7 1289.66  5536.6 1290.49
#Mann=3,-1,0
  3917.4    0.05       0  4993.0    0.05       0  4998.0    0.05       0
Bank Sta=4993,4998
Exp/Cntr=0.3,0.1

Type RM Length L Ch R = 1,31000,500,500,500
BEGIN DESCRIPTION:
NORTH WILLOW CREEK 62.0
END DESCRIPTION:
XS GIS Cut Line= 3
      2743105.69     10256303.12      2742602.74     10255649.42
      2741605.70     10254653.13
#Sta/Elev= 30
  4175.2 1304.15  4510.5 1292.62  4660.0 1290.59  4803.2 1287.35  4838.5 1286.03
  4923.7 1280.65  4931.9 1281.34  4938.2 1280.05  4967.2 1278.66  4979.0 1275.95
  4979.4 1275.45  4984.4 1275.95  5009.5 1276.08  5023.6 1277.49  5037.7 1281.26
  5058.9 1282.16  5165.0 1282.46  5193.3 1281.67  5221.6 1282.20  5355.9 1281.16
  5377.1 1281.83  5412.5 1280.45  5645.8 1287.23  5702.4 1287.90  5709.5 1287.29
  5723.6 1288.47  5808.5 1289.59  5942.8 1293.33  6190.3 1296.96  6409.5 1304.60
#Mann=3,-1,0
  4175.2    0.05       0  4979.0    0.03       0  4984.4    0.05       0
Bank Sta=4979,4984.4
Exp/Cntr=0.3,0.1

Type RM Length L Ch R = 1,30500,500,500,500
BEGIN DESCRIPTION:
NORTH WILLOW CREEK 61.0
END DESCRIPTION:
XS GIS Cut Line= 3
      2743105.69     10256153.13      2742760.93     10255190.61
      2742955.67     10254353.16
#Sta/Elev= 30
  3977.6 1299.09  4284.7 1287.53  4433.2 1285.81  4593.7 1287.63  4721.2 1284.56
  4859.3 1278.50  4965.5 1275.37  4976.2 1273.02  4983.7 1272.89  4984.2 1272.39
  4989.7 1272.89  5048.3 1273.75  5069.3 1274.30  5079.6 1277.56  5091.1 1274.46
  5128.6 1276.36  5133.7 1274.01  5171.2 1278.07  5184.5 1278.22  5213.0 1279.43
  5243.8 1278.85  5351.9 1282.48  5449.2 1288.19  5510.8 1290.39  5521.0 1292.01
  5620.4 1294.86  5645.3 1295.84  5788.0 1301.78  5798.5 1303.17  5859.8 1304.88
#Mann=7,-1,0
  3977.6    0.05       0  4983.7    0.05       0  4989.7    0.05       0
  5048.3    0.12       0  5184.5    0.05       0  5620.4    0.12       0
  5645.3    0.05       0
Bank Sta=4983.7,4989.7
Exp/Cntr=0.3,0.1

Type RM Length L Ch R = 1,30000,500,500,500
BEGIN DESCRIPTION:
NORTH WILLOW CREEK 60.0
END DESCRIPTION:
XS GIS Cut Line= 3
      2743255.68     10256003.10      2743193.37     10255066.67
      2743155.69     10254553.15
#Sta/Elev= 30
  4061.5 1294.65  4136.7 1291.71  4151.7 1292.08  4261.9 1288.68  4382.2 1283.82
  4432.3 1282.72  4437.7 1283.19  4462.4 1281.60  4502.5 1280.85  4522.5 1281.38
  4542.5 1279.70  4622.7 1277.94  4793.1 1276.62  4903.3 1277.61  4913.4 1278.43
  4963.5 1278.30  4973.5 1276.83  4983.5 1273.59  4993.5 1271.45  4996.3 1269.69
  4996.8 1269.19  5002.3 1269.69  5023.6 1273.42  5037.7 1274.24  5043.7 1273.65
  5063.7 1275.82  5103.8 1278.60  5274.3 1288.22  5334.5 1292.83  5514.9 1303.94
#Mann=3,-1,0
  4061.5    0.05       0  4996.3    0.05       0  5002.3    0.05       0
Bank Sta=4996.3,5002.3
Exp/Cntr=0.3,0.1

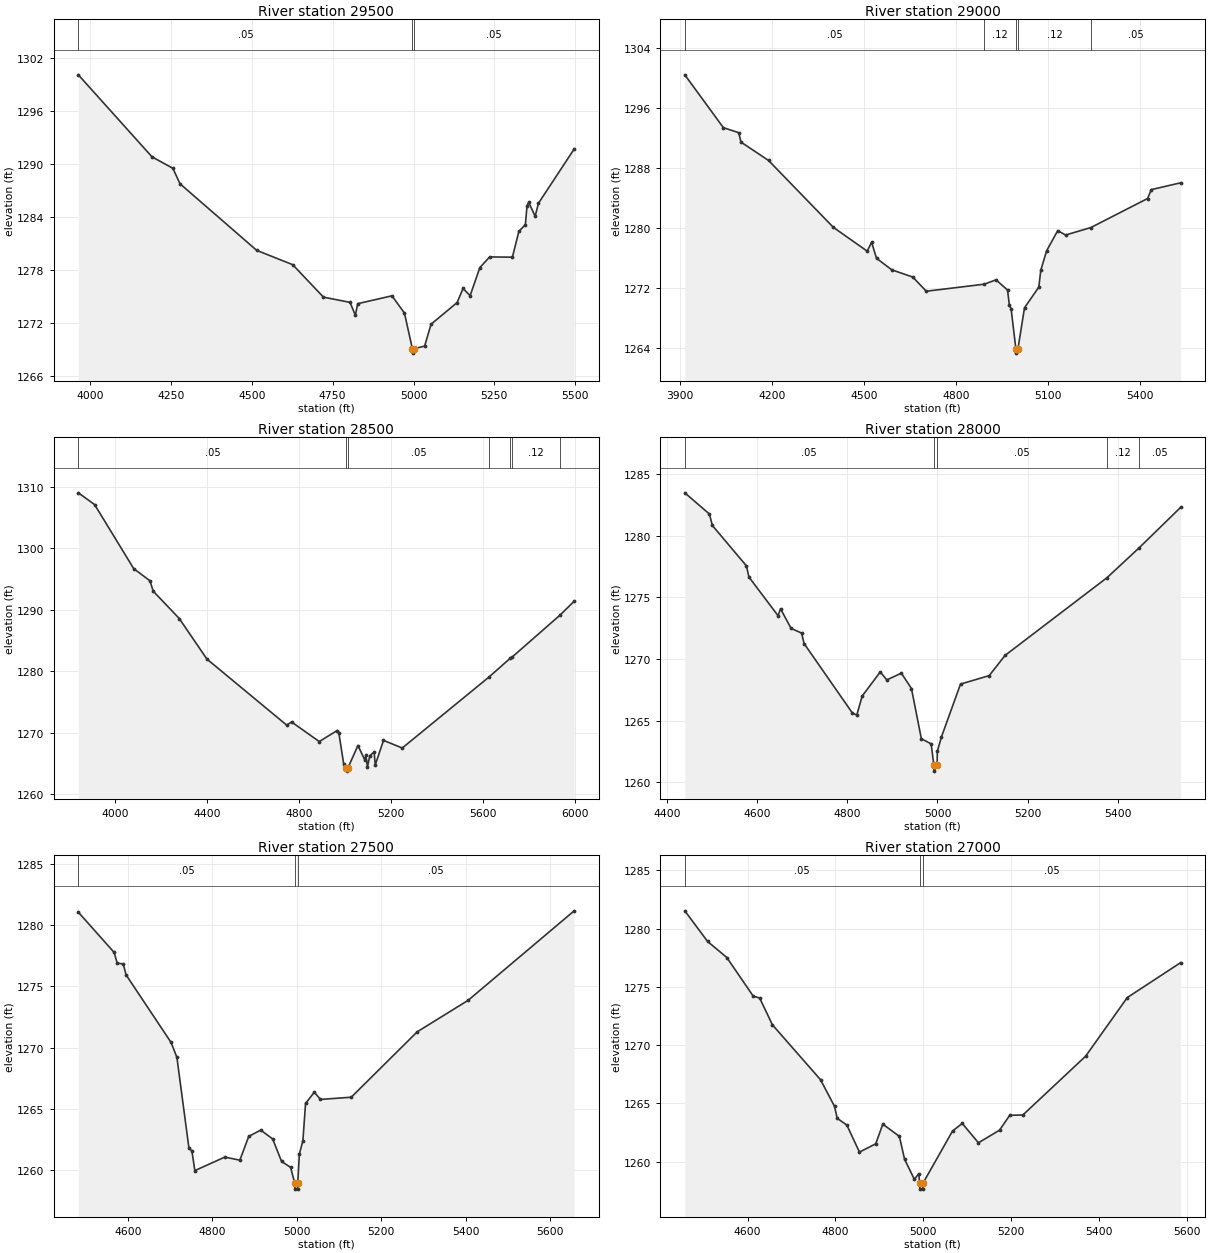
Type RM Length L Ch R = 1,29500,500,500,500
BEGIN DESCRIPTION:
NORTH WILLOW CREEK 59.0
END DESCRIPTION:
XS GIS Cut Line= 3
      2743255.70     10256153.08      2743656.75     10255197.32
      2743605.69     10254703.15
#Sta/Elev= 30
  3963.5 1300.10  4191.2 1290.83  4255.8 1289.53  4278.0 1287.78  4515.1 1280.25
  4626.5 1278.63  4721.5 1274.96  4803.7 1274.37  4820.2 1272.91  4827.4 1274.22
  4933.3 1275.11  4972.0 1273.16  4996.5 1269.13  4997.0 1268.63  5002.6 1269.13
  5034.4 1269.43  5054.3 1271.90  5134.9 1274.35  5153.2 1275.94  5175.1 1275.13
  5205.3 1278.31  5235.5 1279.51  5305.8 1279.48  5325.9 1282.41  5346.0 1283.16
  5351.0 1285.29  5356.1 1285.69  5376.2 1284.11  5386.3 1285.57  5496.8 1291.71
#Mann=3,-1,0
  3963.5    0.05       0  4996.5    0.03       0  5002.6    0.05       0
Bank Sta=4996.5,5002.6
Exp/Cntr=0.3,0.1

Type RM Length L Ch R = 1,29000,500,500,500
BEGIN DESCRIPTION:
NORTH WILLOW CREEK 58.0
END DESCRIPTION:
XS GIS Cut Line= 3
      2743605.71     10256253.07      2744133.51     10255304.53
      2743955.69     10254803.12
#Sta/Elev= 30
  3914.5 1300.46  4040.3 1293.41  4090.5 1292.74  4097.6 1291.49  4187.7 1289.03
  4399.3 1280.10  4509.5 1276.93  4523.9 1278.12  4539.9 1275.98  4589.6 1274.44
  4658.3 1273.47  4702.3 1271.58  4891.3 1272.52  4929.9 1273.10  4967.3 1271.74
  4973.3 1269.77  4979.0 1269.23  4994.8 1263.82  4995.3 1263.32  5001.0 1263.82
  5022.7 1269.37  5069.4 1272.13  5075.8 1274.38  5094.9 1276.98  5131.1 1279.67
  5156.7 1279.08  5239.3 1280.08  5424.0 1283.95  5436.5 1285.14  5532.0 1286.05
#Mann=5,-1,0
  3914.5    0.05       0  4891.3    0.12       0  4994.8    0.07       0
  5001.0    0.12       0  5239.3    0.05       0
Bank Sta=4994.8,5001
Exp/Cntr=0.3,0.1

Type RM Length L Ch R = 1,28500,500,500,500
BEGIN DESCRIPTION:
NORTH WILLOW CREEK 57.0
END DESCRIPTION:
XS GIS Cut Line= 3
      2743605.65     10256453.15      2744442.35     10255649.98
      2745405.72     10255403.10
#Sta/Elev= 30
  3840.2 1309.00  3910.9 1307.09  4080.7 1296.68  4151.4 1294.70  4165.6 1293.01
  4278.8 1288.56  4398.9 1281.97  4745.5 1271.23  4766.9 1271.74  4887.0 1268.56
  4964.7 1270.35  4971.9 1270.02  4993.0 1264.97  5005.0 1264.25  5005.5 1263.75
  5011.2 1264.25  5055.1 1267.91  5084.5 1265.59  5089.6 1266.30  5096.4 1264.42
  5106.7 1266.27  5125.3 1266.85  5130.4 1264.76  5166.1 1268.75  5247.6 1267.51
  5623.6 1279.02  5716.7 1282.10  5725.4 1282.31  5932.9 1289.11  5994.5 1291.37
#Mann=7,-1,0
  3840.2    0.05       0  5005.0    0.05       0  5011.2    0.05       0
  5623.6    0.12       0  5716.7    0.05       0  5725.4    0.12       0
  5932.9    0.05       0
Bank Sta=5005,5011.2
Exp/Cntr=0.3,0.1

Type RM Length L Ch R = 1,28000,500,500,500
BEGIN DESCRIPTION:
NORTH WILLOW CREEK 56.0
END DESCRIPTION:
XS GIS Cut Line= 3
      2744305.66     10256153.12      2744818.48     10255927.89
      2745205.70     10255553.10
#Sta/Elev= 30
  4439.9 1283.48  4494.5 1281.76  4501.0 1280.83  4576.6 1277.55  4582.0 1276.65
  4646.6 1273.51  4652.1 1274.07  4675.5 1272.48  4698.8 1272.10  4704.3 1271.25
  4811.3 1265.62  4821.1 1265.45  4833.1 1266.99  4873.2 1268.95  4887.7 1268.30
  4919.9 1268.85  4942.3 1267.60  4964.2 1263.53  4986.0 1263.11  4991.8 1261.40
  4992.3 1260.90  4999.1 1261.40  4999.7 1262.50  5008.6 1263.66  5051.0 1267.96
  5114.6 1268.65  5149.8 1270.29  5375.9 1276.60  5447.3 1279.03  5538.9 1282.30
#Mann=5,-1,0
  4439.9    0.05       0  4991.8    0.03       0  4999.1    0.05       0
  5375.9    0.12       0  5447.3    0.05       0
Bank Sta=4991.8,4999.1
Exp/Cntr=0.3,0.1

Type RM Length L Ch R = 1,27500,500,500,500
BEGIN DESCRIPTION:
NORTH WILLOW CREEK 55.0
END DESCRIPTION:
XS GIS Cut Line= 3
      2744755.72     10256703.08      2745109.29     10256326.16
      2745505.69     10255803.10
#Sta/Elev= 30
  4483.2 1281.05  4567.9 1277.77  4575.2 1276.90  4589.4 1276.83  4596.2 1275.94
  4702.5 1270.44  4716.4 1269.22  4744.7 1261.87  4752.0 1261.57  4758.9 1259.99
  4829.7 1261.09  4865.4 1260.84  4886.4 1262.78  4914.7 1263.29  4943.0 1262.57
  4964.0 1260.74  4985.5 1260.25  4995.0 1258.98  4995.5 1258.48  5001.8 1258.48
  5002.3 1258.98  5006.2 1261.35  5014.5 1262.43  5020.8 1265.46  5041.6 1266.38
  5056.1 1265.79  5128.9 1265.97  5285.0 1271.30  5405.6 1273.87  5656.3 1281.16
#Mann=3,-1,0
  4483.2    0.05       0  4995.0    0.05       0  5002.3    0.05       0
Bank Sta=4995,5002.3
Exp/Cntr=0.3,0.1

Type RM Length L Ch R = 1,27000,500,500,500
BEGIN DESCRIPTION:
NORTH WILLOW CREEK 54.0
END DESCRIPTION:
XS GIS Cut Line= 3
      2744855.64     10256903.13      2745333.39     10256645.48
      2745555.70     10256103.07
#Sta/Elev= 30
  4457.2 1281.53  4509.1 1278.90  4552.9 1277.52  4612.9 1274.21  4627.7 1274.04
  4656.7 1271.74  4766.2 1267.03  4798.1 1264.74  4804.3 1263.71  4826.2 1263.13
  4854.9 1260.81  4891.9 1261.52  4908.1 1263.21  4945.8 1262.16  4957.6 1260.20
  4979.9 1258.47  4990.0 1258.96  4991.9 1258.13  4992.4 1257.63  4998.9 1257.63
  4999.4 1258.13  5067.0 1262.63  5089.0 1263.27  5125.8 1261.61  5173.8 1262.69
  5197.1 1263.97  5227.1 1264.00  5370.0 1269.05  5464.7 1274.08  5586.2 1277.08
#Mann=3,-1,0
  4457.2    0.05       0  4991.9    0.05       0  4999.4    0.05       0
Bank Sta=4991.9,4999.4
Exp/Cntr=0.3,0.1

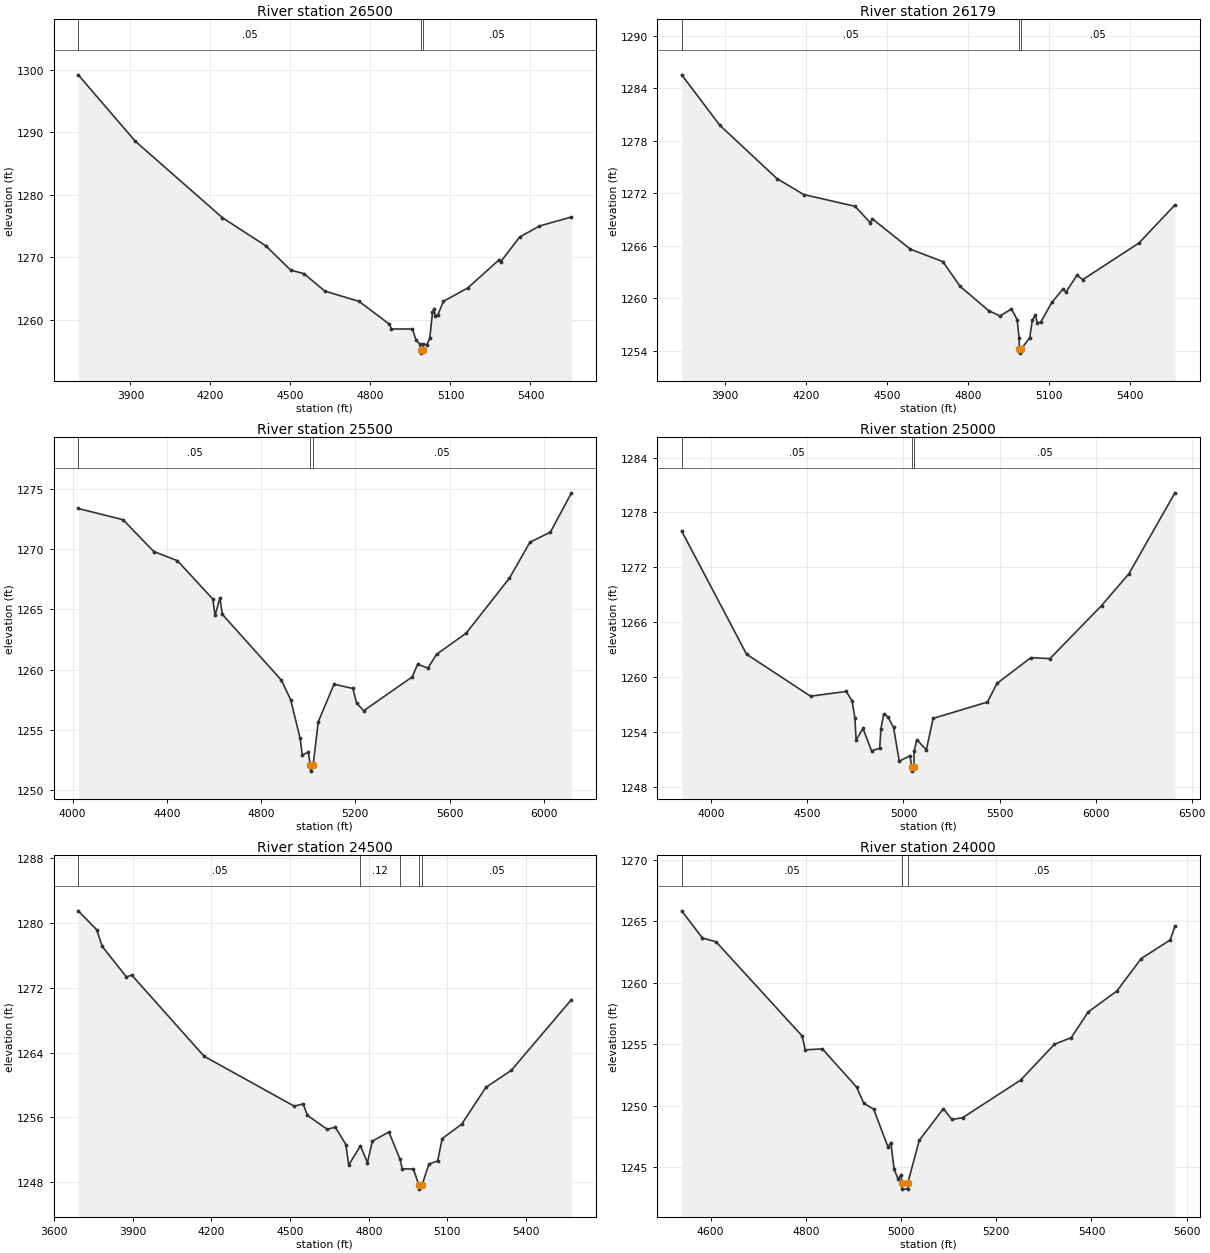
Type RM Length L Ch R = 1,26500,321,321,321
BEGIN DESCRIPTION:
NORTH WILLOW CREEK 53.0
END DESCRIPTION:
XS GIS Cut Line= 3
      2744805.65     10257553.14      2745818.57     10256745.15
      2745705.68     10256203.09
#Sta/Elev= 30
  3704.3 1299.18  3918.1 1288.58  4244.8 1276.36  4408.1 1271.84  4501.0 1267.97
  4550.6 1267.41  4629.1 1264.62  4757.2 1262.98  4870.9 1259.34  4878.9 1258.57
  4957.4 1258.56  4970.7 1256.82  4984.6 1256.18  4988.8 1255.21  4989.3 1254.71
  4996.3 1255.21  4997.6 1256.12  5012.3 1256.08  5022.5 1257.11  5032.7 1261.21
  5038.3 1261.82  5043.4 1260.62  5053.2 1260.88  5073.6 1262.98  5165.5 1265.14
  5283.5 1269.67  5288.6 1269.32  5359.6 1273.26  5433.6 1275.02  5553.7 1276.46
#Mann=3,-1,0
  3704.3    0.05       0  4988.8    0.05       0  4996.3    0.05       0
Bank Sta=4988.8,4996.3
Exp/Cntr=0.3,0.1

Type RM Length L Ch R = 1,26179,679,679,679
BEGIN DESCRIPTION:
NORTH WILLOW CREEK 52.0
END DESCRIPTION:
XS GIS Cut Line= 3
      2745205.69     10257803.11      2746087.50     10256901.00
      2745933.06     10256353.98
#Sta/Elev= 30
  3738.5 1285.53  3879.9 1279.76  4092.0 1273.66  4191.0 1271.84  4381.9 1270.49
  4438.5 1268.60  4445.7 1269.06  4587.1 1265.58  4707.3 1264.17  4771.0 1261.35
  4877.0 1258.56  4919.4 1257.95  4961.9 1258.75  4983.1 1257.53  4990.2 1255.39
  4991.3 1254.20  4991.8 1253.70  4998.9 1254.20  5029.6 1255.47  5039.4 1257.49
  5049.8 1258.02  5058.4 1257.16  5070.5 1257.25  5112.1 1259.52  5153.7 1261.05
  5164.1 1260.68  5204.8 1262.61  5226.4 1262.11  5434.7 1266.29  5568.4 1270.65
#Mann=3,-1,0
  3738.5    0.05       0  4991.3    0.03       0  4998.9    0.05       0
Bank Sta=4991.3,4998.9
Exp/Cntr=0.3,0.1

Type RM Length L Ch R = 1,25500,500,500,500
BEGIN DESCRIPTION:
NORTH WILLOW CREEK 51.0
END DESCRIPTION:
XS GIS Cut Line= 3
      2746605.69     10258103.15      2746549.47     10257128.77
      2746005.67     10256153.08
#Sta/Elev= 30
  4024.0 1273.38  4214.4 1272.45  4344.6 1269.81  4444.7 1269.05  4595.0 1265.87
  4605.0 1264.51  4625.0 1265.97  4635.9 1264.59  4885.5 1259.15  4925.5 1257.52
  4965.6 1254.31  4974.8 1252.94  5000.0 1253.15  5009.4 1252.09  5009.9 1251.59
  5020.8 1252.09  5042.6 1255.68  5109.5 1258.80  5189.6 1258.45  5204.9 1257.25
  5235.4 1256.60  5441.5 1259.41  5464.3 1260.46  5507.8 1260.14  5544.5 1261.28
  5670.1 1263.03  5853.7 1267.60  5940.9 1270.58  6027.8 1271.42  6117.0 1274.68
#Mann=3,-1,0
  4024.0    0.05       0  5009.4    0.03       0  5020.8    0.05       0
Bank Sta=5009.4,5020.8
Exp/Cntr=0.3,0.1

Type RM Length L Ch R = 1,25000,500,500,500
BEGIN DESCRIPTION:
NORTH WILLOW CREEK 50.0
END DESCRIPTION:
XS GIS Cut Line= 3
      2747655.70     10257903.13      2747012.03     10256945.20
      2746005.72     10255953.14
#Sta/Elev= 30
  3845.9 1275.95  4183.5 1262.48  4516.4 1257.89  4702.5 1258.41  4732.5 1257.37
  4747.4 1255.53  4753.5 1253.09  4789.5 1254.36  4833.8 1251.91  4876.5 1252.19
  4882.5 1254.30  4897.5 1255.94  4918.5 1255.65  4948.5 1254.47  4978.4 1250.77
  5034.3 1251.38  5042.4 1250.19  5042.9 1249.69  5054.5 1250.19  5055.4 1251.84
  5069.6 1253.14  5119.1 1252.01  5154.4 1255.46  5437.3 1257.25  5486.8 1259.29
  5663.6 1262.11  5762.6 1262.00  6031.3 1267.81  6172.8 1271.27  6413.1 1280.14
#Mann=3,-1,0
  3845.9    0.05       0  5042.4    0.03       0  5054.5    0.05       0
Bank Sta=5042.4,5054.5
Exp/Cntr=0.3,0.1

Type RM Length L Ch R = 1,24500,500,500,500
BEGIN DESCRIPTION:
NORTH WILLOW CREEK 49.0
END DESCRIPTION:
XS GIS Cut Line= 3
      2747705.68     10258003.08      2747444.13     10256722.52
      2747505.68     10256153.13
#Sta/Elev= 30
  3693.0 1281.47  3763.6 1279.14  3784.8 1277.08  3876.7 1273.33  3897.1 1273.55
  4172.7 1263.55  4516.0 1257.40  4550.3 1257.67  4566.5 1256.26  4642.2 1254.54
  4672.8 1254.81  4713.0 1252.67  4723.8 1250.15  4768.5 1252.49  4795.3 1250.45
  4814.0 1253.09  4876.9 1254.21  4919.3 1250.87  4927.9 1249.67  4970.6 1249.65
  4991.0 1247.67  4991.5 1247.17  5003.2 1247.67  5029.6 1250.27  5062.9 1250.64
  5079.9 1253.39  5154.7 1255.18  5246.4 1259.71  5343.3 1261.80  5572.7 1270.53
#Mann=5,-1,0
  3693.0    0.05       0  4768.5    0.12       0  4919.3    0.05       0
  4991.0    0.03       0  5003.2    0.05       0
Bank Sta=4991,5003.2
Exp/Cntr=0.3,0.1

Type RM Length L Ch R = 1,24000,500,500,500
BEGIN DESCRIPTION:
NORTH WILLOW CREEK 48.0
END DESCRIPTION:
XS GIS Cut Line= 3
      2748105.67     10257353.10      2747848.29     10256971.00
      2747755.68     10256403.10
#Sta/Elev= 30
  4539.3 1265.83  4582.8 1263.62  4611.6 1263.31  4792.5 1255.65  4798.7 1254.53
  4834.7 1254.61  4906.6 1251.51  4921.6 1250.20  4942.6 1249.70  4972.6 1246.64
  4978.6 1246.99  4985.4 1244.85  4993.6 1244.06  5000.0 1244.32  5001.8 1243.71
  5002.3 1243.21  5013.6 1243.21  5014.1 1243.71  5038.4 1247.18  5089.0 1249.75
  5106.8 1248.87  5129.6 1249.02  5251.2 1252.07  5322.1 1254.98  5357.7 1255.53
  5393.0 1257.60  5453.8 1259.33  5504.5 1261.95  5565.3 1263.46  5575.4 1264.58
#Mann=3,-1,0
  4539.3    0.05       0  5001.8    0.05       0  5014.1    0.05       0
Bank Sta=5001.8,5014.1
Exp/Cntr=0.3,0.1