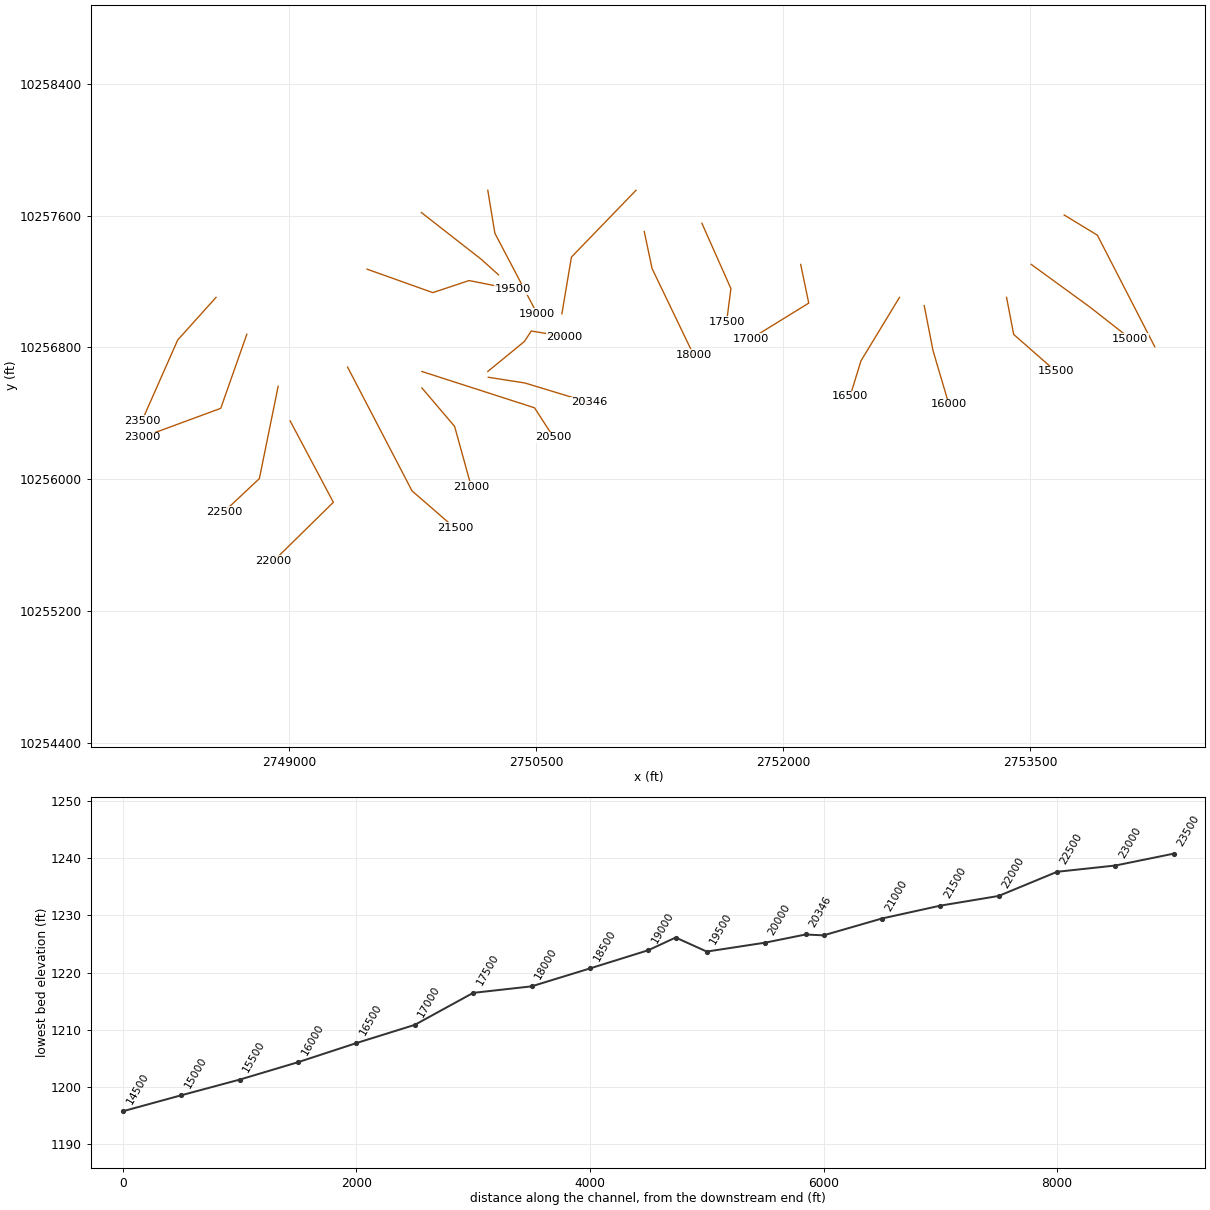
HEC-RAS study NORTH WILLOW CREEK.prj: NORTH WILLOW CREEK Base Level Engineering

--- NORTH WILLOW CREEK.g01 (geometry) --- (continued)

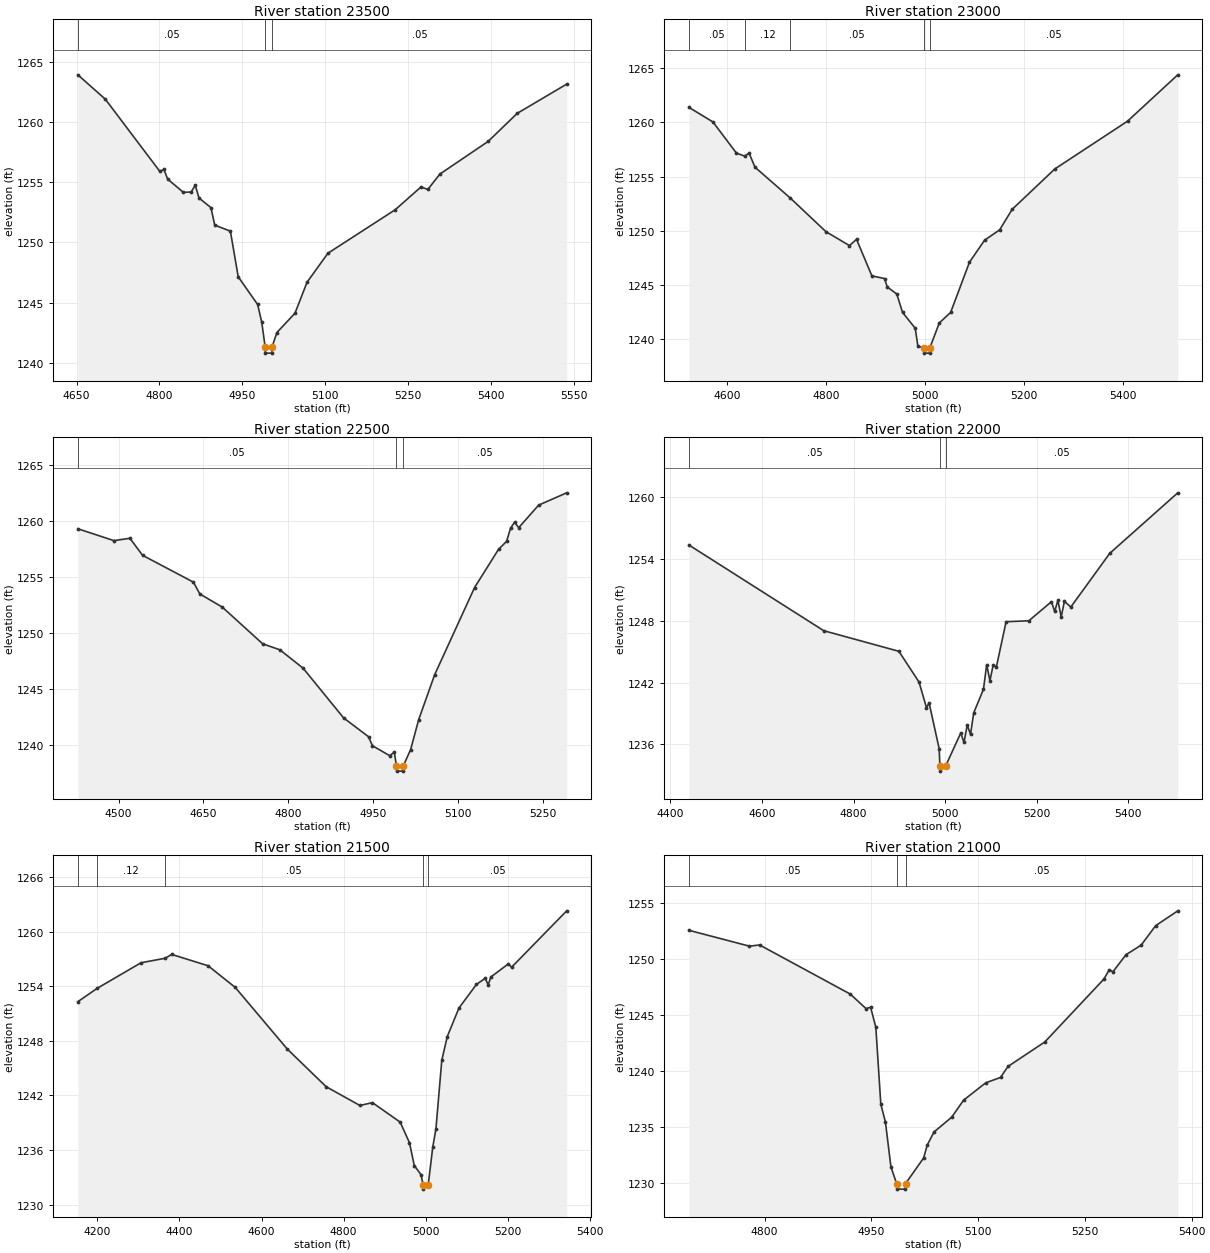
Type RM Length L Ch R = 1,23500,500,500,500
BEGIN DESCRIPTION:
NORTH WILLOW CREEK 47.0
END DESCRIPTION:
XS GIS Cut Line= 3
      2748555.68     10257103.11      2748323.05     10256844.70
      2748105.68     10256353.11
#Sta/Elev= 30
  4652.3 1263.91  4702.0 1261.89  4800.7 1255.90  4808.1 1256.06  4814.9 1255.26
  4843.3 1254.16  4857.5 1254.19  4864.9 1254.75  4871.7 1253.69  4893.3 1252.89
  4900.1 1251.44  4928.5 1250.94  4942.7 1247.15  4977.8 1244.86  4985.3 1243.39
  4991.5 1241.32  4992.0 1240.82  5003.4 1240.82  5003.9 1241.32  5012.7 1242.53
  5045.5 1244.13  5067.3 1246.70  5105.2 1249.11  5227.1 1252.72  5273.7 1254.61
  5286.0 1254.40  5308.0 1255.68  5395.4 1258.39  5447.8 1260.71  5537.5 1263.14
#Mann=3,-1,0
  4652.3    0.05       0  4991.5    0.03       0  5003.9    0.05       0
Bank Sta=4991.5,5003.9
Exp/Cntr=0.3,0.1

Type RM Length L Ch R = 1,23000,500,500,500
BEGIN DESCRIPTION:
NORTH WILLOW CREEK 46.0
END DESCRIPTION:
XS GIS Cut Line= 3
      2748742.39     10256878.74      2748584.24     10256429.35
      2748105.66     10256253.10
#Sta/Elev= 30
  4523.6 1261.39  4572.0 1260.05  4619.4 1257.18  4636.0 1256.90  4645.1 1257.17
  4656.8 1255.88  4728.0 1253.04  4799.9 1249.94  4847.6 1248.65  4861.8 1249.23
  4892.8 1245.86  4918.4 1245.61  4923.7 1244.84  4943.0 1244.19  4954.7 1242.49
  4980.3 1241.03  4985.6 1239.38  4997.5 1239.24  4998.0 1238.74  5009.4 1238.74
  5009.9 1239.24  5028.8 1241.52  5051.7 1242.49  5089.7 1247.12  5120.2 1249.15
  5150.6 1250.10  5175.8 1251.99  5261.8 1255.71  5408.7 1260.12  5510.0 1264.39
#Mann=5,-1,0
  4523.6    0.05       0  4636.0    0.12       0  4728.0    0.05       0
  4997.5    0.05       0  5009.9    0.05       0
Bank Sta=4997.5,5009.9
Exp/Cntr=0.3,0.1

Type RM Length L Ch R = 1,22500,500,500,500
BEGIN DESCRIPTION:
NORTH WILLOW CREEK 45.0
END DESCRIPTION:
XS GIS Cut Line= 3
      2748932.86     10256563.26      2748818.73     10256002.76
      2748605.66     10255803.09
#Sta/Elev= 30
  4428.0 1259.29  4491.7 1258.23  4520.0 1258.44  4542.3 1256.92  4632.3 1254.52
  4643.5 1253.47  4683.3 1252.29  4754.7 1249.01  4785.0 1248.48  4826.2 1246.83
  4897.6 1242.40  4941.8 1240.71  4948.6 1239.91  4979.2 1239.02  4987.3 1239.33
  4991.0 1238.14  4991.5 1237.64  5003.0 1237.64  5003.5 1238.14  5016.2 1239.57
  5030.4 1242.24  5058.7 1246.26  5129.1 1254.03  5171.6 1257.46  5185.7 1258.16
  5193.0 1259.37  5199.9 1259.86  5207.2 1259.39  5242.4 1261.40  5292.0 1262.50
#Mann=3,-1,0
  4428.0    0.05       0  4991.0    0.03       0  5003.5    0.05       0
Bank Sta=4991,5003.5
Exp/Cntr=0.3,0.1

Type RM Length L Ch R = 1,22000,500,500,500
BEGIN DESCRIPTION:
NORTH WILLOW CREEK 44.0
END DESCRIPTION:
XS GIS Cut Line= 3
      2749005.71     10256353.07      2749268.05     10255859.00
      2748905.69     10255503.12
#Sta/Elev= 30
  4440.6 1255.34  4734.9 1247.03  4899.0 1245.03  4943.0 1242.05  4959.3 1239.56
  4965.0 1240.02  4987.0 1235.58  4988.6 1233.91  4989.1 1233.41  5001.1 1233.91
  5034.1 1237.11  5041.2 1236.19  5048.2 1237.88  5055.4 1236.98  5062.4 1239.06
  5083.7 1241.35  5090.7 1243.74  5097.8 1242.17  5104.8 1243.69  5111.9 1243.52
  5133.1 1247.90  5182.7 1247.99  5232.1 1249.84  5239.2 1248.90  5246.2 1249.97
  5253.4 1248.37  5260.4 1249.87  5274.5 1249.33  5359.4 1254.53  5507.9 1260.40
#Mann=3,-1,0
  4440.6    0.05       0  4988.6    0.03       0  5001.1    0.05       0
Bank Sta=4988.6,5001.1
Exp/Cntr=0.3,0.1

Type RM Length L Ch R = 1,21500,500,500,500
BEGIN DESCRIPTION:
NORTH WILLOW CREEK 43.0
END DESCRIPTION:
XS GIS Cut Line= 3
      2749354.35     10256679.82      2749745.85     10255928.05
      2750005.70     10255703.10
#Sta/Elev= 30
  4152.4 1252.30  4199.6 1253.77  4306.5 1256.58  4365.2 1257.07  4381.2 1257.49
  4469.6 1256.25  4535.9 1253.87  4662.9 1247.09  4757.5 1242.96  4839.7 1240.90
  4870.3 1241.21  4937.9 1239.07  4960.5 1236.81  4972.3 1234.30  4988.7 1233.30
  4993.7 1232.21  4994.2 1231.71  5006.3 1232.21  5017.4 1236.36  5025.0 1238.31
  5039.3 1245.86  5052.7 1248.47  5081.0 1251.59  5123.8 1254.20  5145.3 1254.87
  5152.3 1254.14  5158.9 1255.01  5201.7 1256.46  5209.3 1256.08  5343.7 1262.28
#Mann=5,-1,0
  4152.4    0.05       0  4199.6    0.12       0  4365.2    0.05       0
  4993.7    0.03       0  5006.3    0.05       0
Bank Sta=4993.7,5006.3
Exp/Cntr=0.3,0.1

Type RM Length L Ch R = 1,21000,500,500,500
BEGIN DESCRIPTION:
NORTH WILLOW CREEK 42.0
END DESCRIPTION:
XS GIS Cut Line= 3
      2749805.71     10256553.08      2750004.21     10256319.81
      2750105.69     10255953.09
#Sta/Elev= 30
  4693.7 1252.59  4778.8 1251.17  4793.0 1251.28  4920.4 1246.89  4942.4 1245.60
  4949.0 1245.70  4956.3 1243.92  4963.3 1237.05  4969.8 1235.45  4977.5 1231.45
  4985.5 1229.96  4986.0 1229.46  4997.6 1229.46  4998.1 1229.96  5023.4 1232.24
  5028.6 1233.41  5038.1 1234.57  5062.9 1235.89  5079.6 1237.41  5110.7 1238.96
  5131.5 1239.44  5141.9 1240.42  5193.7 1242.61  5276.7 1248.23  5284.3 1249.06
  5289.5 1248.89  5307.8 1250.41  5329.0 1251.26  5349.4 1253.00  5380.5 1254.33
#Mann=3,-1,0
  4693.7    0.05       0  4985.5    0.03       0  4998.1    0.05       0
Bank Sta=4985.5,4998.1
Exp/Cntr=0.3,0.1

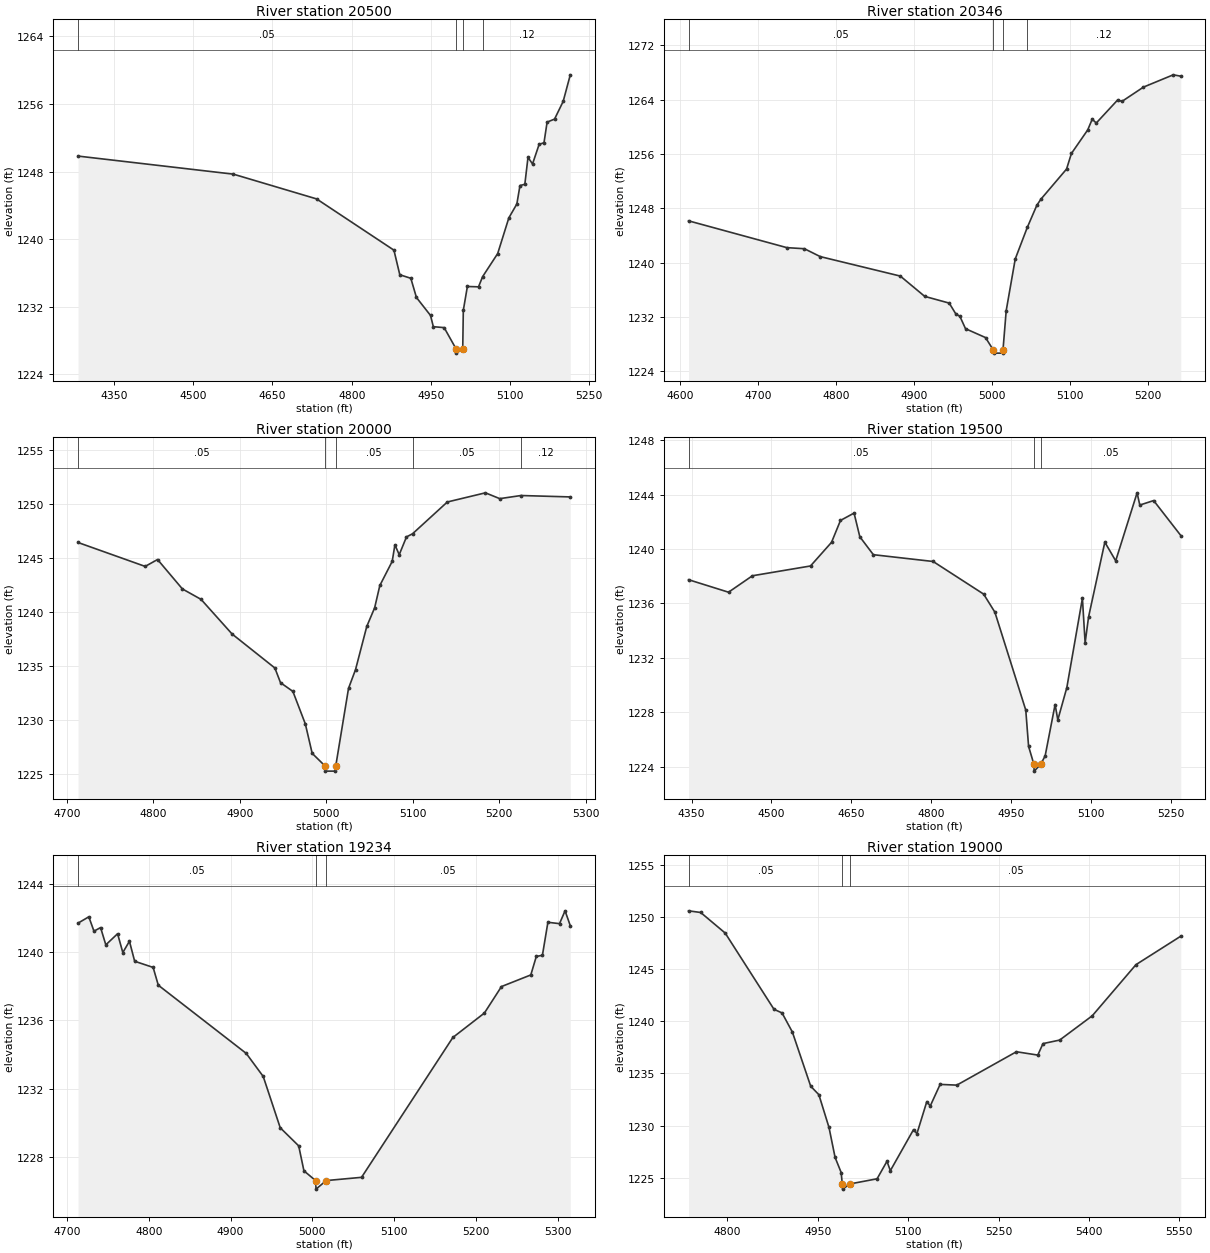
Type RM Length L Ch R = 1,20500,154,154,154
BEGIN DESCRIPTION:
NORTH WILLOW CREEK 41.0
END DESCRIPTION:
XS GIS Cut Line= 3
      2749805.69     10256653.11      2750489.35     10256432.71
      2750605.69     10256253.10
#Sta/Elev= 30
  4281.7 1249.84  4575.9 1247.70  4733.5 1244.77  4880.0 1238.70  4891.1 1235.79
  4912.0 1235.37  4922.6 1233.10  4949.3 1230.97  4954.6 1229.64  4975.1 1229.53
  4997.7 1227.01  4998.2 1226.51  5010.3 1227.01  5011.4 1231.58  5019.1 1234.40
  5040.2 1234.36  5048.0 1235.57  5076.5 1238.30  5097.6 1242.52  5112.8 1244.17
  5118.7 1246.35  5127.9 1246.50  5133.9 1249.69  5142.5 1248.91  5155.0 1251.23
  5164.2 1251.42  5170.1 1253.86  5184.2 1254.22  5200.5 1256.31  5214.0 1259.46
#Mann=4,-1,0
  4281.7    0.05       0  4997.7    0.03       0  5010.3    0.05       0
  5048.0    0.12       0
Bank Sta=4997.7,5010.3
Exp/Cntr=0.3,0.1

Type RM Length L Ch R = 1,20346,346,346,346
BEGIN DESCRIPTION:
Mapping XS 4d85bba2
END DESCRIPTION:
XS GIS Cut Line= 3
      2750208.82     10256618.02      2750431.01     10256583.30
      2750819.90     10256465.24
#Sta/Elev= 30
  4610.6 1246.15  4736.7 1242.20  4759.2 1242.04  4779.5 1240.88  4882.2 1238.01
  4913.5 1235.02  4944.9 1234.03  4953.4 1232.43  4958.6 1232.08  4965.8 1230.26
  4991.5 1228.95  5001.2 1227.16  5001.7 1226.66  5013.4 1226.66  5013.9 1227.16
  5018.0 1232.93  5029.6 1240.54  5045.0 1245.17  5057.3 1248.45  5062.5 1249.34
  5095.4 1253.78  5101.6 1256.07  5122.5 1259.54  5128.3 1261.12  5133.5 1260.56
  5161.1 1263.98  5166.4 1263.74  5194.0 1265.85  5232.2 1267.66  5241.9 1267.46
#Mann=4,-1,0
  4610.6    0.05       0  5001.2    0.03       0  5013.9    0.05       0
  5045.0    0.12       0
Bank Sta=5001.2,5013.9
Exp/Cntr=0.3,0.1

Type RM Length L Ch R = 1,20000,500,500,500
BEGIN DESCRIPTION:
NORTH WILLOW CREEK 40.0
END DESCRIPTION:
XS GIS Cut Line= 4
      2750205.68     10256653.11      2750427.64     10256834.90
      2750469.86     10256898.84      2750672.40     10256864.83
#Sta/Elev= 30
  4713.1 1246.45  4790.7 1244.23  4805.0 1244.87  4833.7 1242.14  4855.3 1241.17
  4891.1 1237.96  4940.6 1234.80  4947.1 1233.44  4961.4 1232.63  4975.8 1229.61
  4983.7 1226.88  4998.3 1225.73  4998.8 1225.23  5010.5 1225.23  5011.0 1225.73
  5025.7 1232.91  5033.8 1234.65  5046.8 1238.66  5055.9 1240.39  5061.9 1242.46
  5076.2 1244.70  5079.3 1246.23  5084.3 1245.32  5092.7 1246.97  5099.7 1247.26
  5139.9 1250.21  5183.9 1251.06  5200.5 1250.52  5225.0 1250.81  5282.0 1250.68
#Mann=5,-1,0
  4713.1    0.05       0  4998.3    0.05       0  5011.0    0.05       0
  5099.7    0.05       0  5225.0    0.12       0
Bank Sta=4998.3,5011
Exp/Cntr=0.3,0.1

Type RM Length L Ch R = 1,19500,266,266,266
BEGIN DESCRIPTION:
NORTH WILLOW CREEK 39.0
END DESCRIPTION:
XS GIS Cut Line= 4
      2749472.67     10257274.27      2749871.99     10257131.91
      2750091.89     10257205.12      2750355.71     10257153.11
#Sta/Elev= 30
  4344.3 1237.75  4419.4 1236.83  4464.3 1238.04  4573.4 1238.76  4612.9 1240.50
  4629.7 1242.11  4655.2 1242.65  4666.0 1240.91  4691.4 1239.59  4803.7 1239.09
  4898.6 1236.69  4919.7 1235.36  4977.7 1228.16  4983.0 1225.49  4993.0 1224.17
  4993.5 1223.67  5005.7 1224.17  5014.1 1224.79  5032.8 1228.57  5037.9 1227.44
  5054.8 1229.81  5084.1 1236.38  5089.2 1233.10  5095.6 1235.00  5126.2 1240.51
  5146.6 1239.14  5186.8 1244.14  5191.9 1243.24  5217.9 1243.57  5268.9 1241.00
#Mann=3,-1,0
  4344.3    0.05       0  4993.0    0.05       0  5005.7    0.05       0
Bank Sta=4993,5005.7
Exp/Cntr=0.3,0.1

Type RM Length L Ch R = 1,19234,234,234,234
BEGIN DESCRIPTION:
Mapping XS 97587a68
END DESCRIPTION:
XS GIS Cut Line= 3
      2749802.58     10257617.99      2750167.13     10257333.30
      2750271.01     10257239.81
#Sta/Elev= 30
  4713.3 1241.69  4726.5 1242.06  4732.8 1241.22  4740.9 1241.43  4747.3 1240.42
  4761.7 1241.07  4768.1 1239.97  4776.2 1240.63  4782.6 1239.46  4805.2 1239.10
  4811.5 1238.06  4919.1 1234.07  4939.9 1232.72  4960.7 1229.72  4983.3 1228.66
  4989.7 1227.20  5004.0 1226.63  5004.5 1226.13  5016.9 1226.63  5060.2 1226.82
  5171.9 1235.00  5210.5 1236.43  5231.4 1237.98  5267.3 1238.66  5274.0 1239.74
  5281.5 1239.81  5288.2 1241.74  5302.4 1241.66  5309.2 1242.41  5315.6 1241.54
#Mann=3,-1,0
  4713.3    0.05       0  5004.0    0.05       0  5016.9    0.05       0
Bank Sta=5004,5016.9
Exp/Cntr=0.3,0.1

Type RM Length L Ch R = 1,19000,500,500,500
BEGIN DESCRIPTION:
NORTH WILLOW CREEK 38.0
END DESCRIPTION:
XS GIS Cut Line= 3
      2750205.69     10257753.06      2750248.81     10257492.00
      2750505.70     10257003.08
#Sta/Elev= 30
  4735.4 1250.59  4755.6 1250.43  4796.2 1248.46  4877.2 1241.15  4890.6 1240.80
  4907.7 1238.97  4938.1 1233.78  4951.7 1232.96  4968.5 1229.82  4978.6 1226.95
  4988.7 1225.50  4990.5 1224.41  4991.0 1223.91  5003.4 1224.41  5048.3 1224.90
  5064.7 1226.58  5070.3 1225.68  5108.8 1229.62  5114.4 1229.23  5130.8 1232.30
  5136.5 1231.88  5152.9 1233.95  5180.6 1233.88  5279.5 1237.08  5315.0 1236.76
  5323.6 1237.86  5351.3 1238.20  5405.4 1240.53  5477.9 1245.43  5552.3 1248.16
#Mann=3,-1,0
  4735.4    0.05       0  4990.5    0.05       0  5003.4    0.05       0
Bank Sta=4990.5,5003.4
Exp/Cntr=0.3,0.1

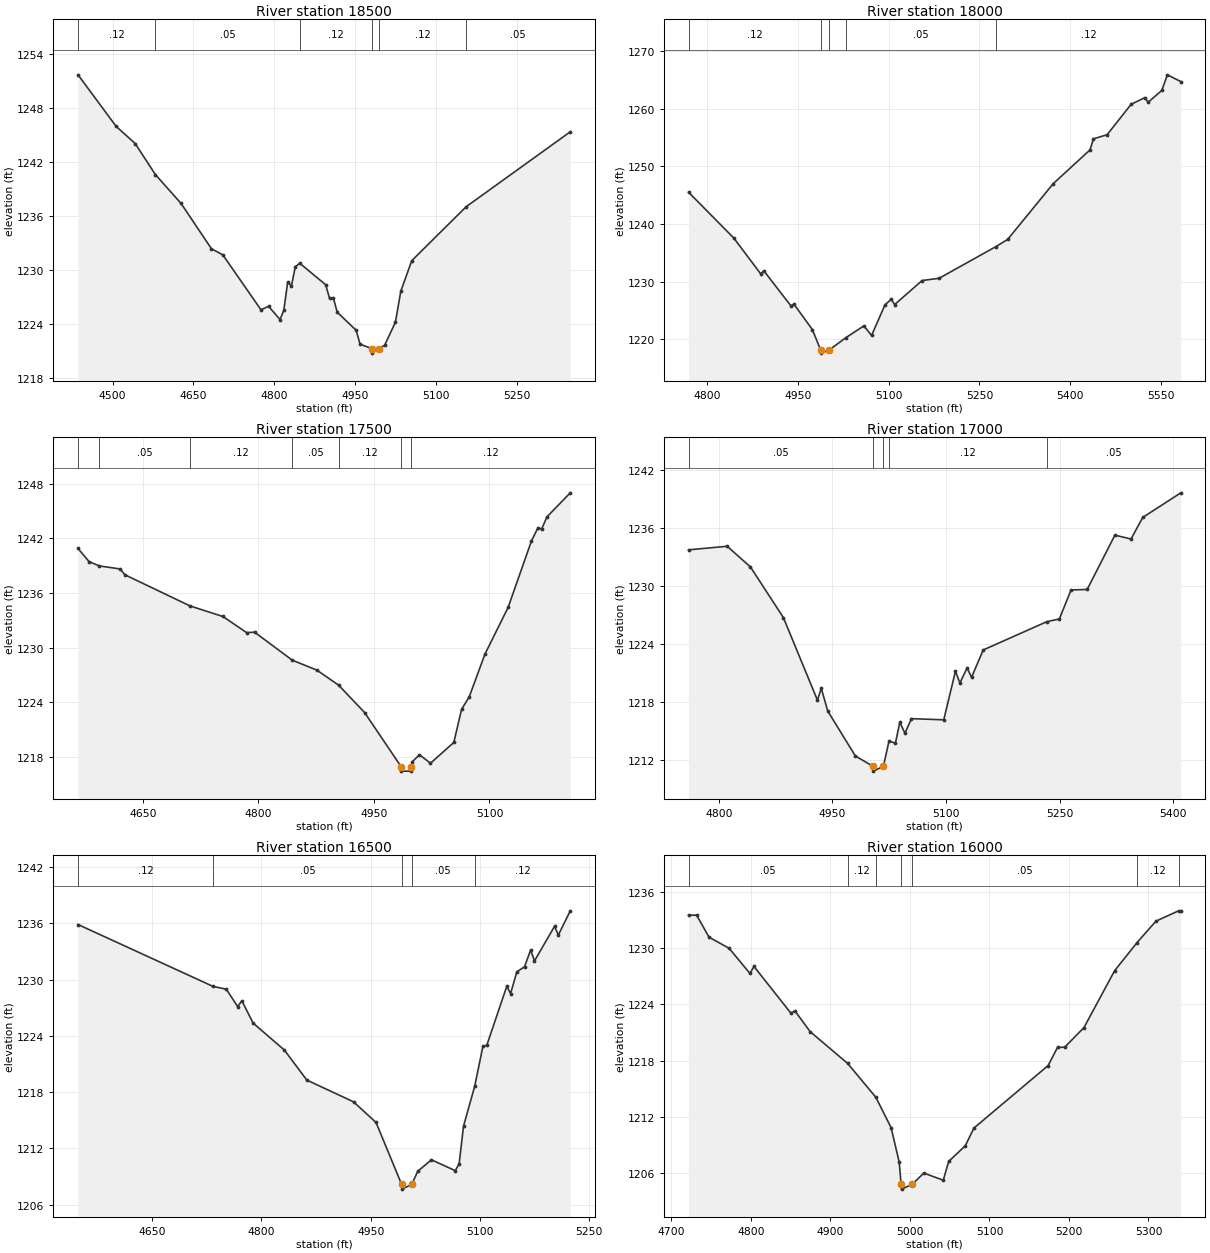
Type RM Length L Ch R = 1,18500,500,500,500
BEGIN DESCRIPTION:
NORTH WILLOW CREEK 37.0
END DESCRIPTION:
XS GIS Cut Line= 3
      2751105.66     10257753.09      2750713.60     10257347.64
      2750655.68     10257003.08
#Sta/Elev= 30
  4436.0 1251.65  4506.6 1245.93  4542.1 1244.01  4579.7 1240.55  4627.0 1237.37
  4683.6 1232.32  4704.7 1231.64  4775.4 1225.54  4789.6 1225.92  4810.9 1224.45
  4817.8 1225.47  4825.0 1228.59  4832.0 1228.20  4839.2 1230.33  4847.6 1230.70
  4895.5 1228.32  4902.7 1226.81  4909.7 1226.88  4916.9 1225.27  4952.1 1223.26
  4959.3 1221.72  4981.2 1221.22  4981.7 1220.72  4994.1 1221.22  5004.8 1221.58
  5024.9 1224.15  5035.0 1227.62  5055.3 1231.00  5156.4 1237.00  5349.4 1245.32
#Mann=6,-1,0
  4436.0    0.12       0  4579.7    0.05       0  4847.6    0.12       0
  4981.2    0.07       0  4994.1    0.12       0  5156.4    0.05       0
Bank Sta=4981.2,4994.1
Exp/Cntr=0.3,0.1

Type RM Length L Ch R = 1,18000,500,500,500
BEGIN DESCRIPTION:
NORTH WILLOW CREEK 36.0
END DESCRIPTION:
XS GIS Cut Line= 3
      2751155.68     10257503.12      2751203.30     10257278.00
      2751455.68     10256753.12
#Sta/Elev= 30
  4769.9 1245.51  4844.5 1237.56  4889.1 1231.33  4894.2 1231.87  4938.8 1225.79
  4943.9 1226.07  4974.3 1221.67  4988.1 1218.08  4988.6 1217.58  5001.5 1218.08
  5029.0 1220.22  5059.3 1222.31  5072.0 1220.65  5094.2 1225.97  5104.5 1226.93
  5110.1 1226.01  5155.4 1230.18  5183.5 1230.57  5277.3 1236.07  5296.7 1237.32
  5371.6 1246.97  5432.5 1252.85  5438.2 1254.77  5460.7 1255.48  5500.4 1260.76
  5523.1 1261.93  5528.6 1261.12  5551.2 1263.19  5560.2 1265.88  5582.4 1264.71
#Mann=5,-1,0
  4769.9    0.12       0  4988.1    0.07       0  5001.5    0.12       0
  5029.0    0.05       0  5277.3    0.12       0
Bank Sta=4988.1,5001.5
Exp/Cntr=0.3,0.1

Type RM Length L Ch R = 1,17500,500,500,500
BEGIN DESCRIPTION:
NORTH WILLOW CREEK 35.0
END DESCRIPTION:
XS GIS Cut Line= 3
      2751505.67     10257553.13      2751681.95     10257156.32
      2751655.68     10256953.11
#Sta/Elev= 30
  4565.8 1240.89  4580.2 1239.44  4593.6 1238.97  4620.5 1238.64  4626.7 1238.00
  4711.2 1234.58  4753.9 1233.42  4784.7 1231.65  4795.0 1231.70  4844.0 1228.62
  4875.7 1227.54  4904.0 1225.89  4937.9 1222.87  4985.2 1216.94  4985.7 1216.44
  4998.2 1216.44  4998.7 1216.94  5000.0 1217.49  5009.1 1218.24  5023.4 1217.31
  5053.7 1219.59  5063.7 1223.21  5073.8 1224.62  5094.0 1229.27  5124.2 1234.42
  5154.5 1241.72  5162.7 1243.12  5167.8 1243.05  5174.7 1244.37  5204.9 1247.00
#Mann=7,-1,0
  4565.8    0.12       0  4593.6    0.05       0  4711.2    0.12       0
  4844.0    0.05       0  4904.0    0.12       0  4985.2    0.07       0
  4998.7    0.12       0
Bank Sta=4985.2,4998.7
Exp/Cntr=0.3,0.1

Type RM Length L Ch R = 1,17000,500,500,500
BEGIN DESCRIPTION:
NORTH WILLOW CREEK 34.0
END DESCRIPTION:
XS GIS Cut Line= 3
      2752105.69     10257303.07      2752154.57     10257068.20
      2751805.65     10256853.09
#Sta/Elev= 30
  4760.1 1233.74  4811.1 1234.11  4841.8 1231.97  4885.3 1226.73  4930.2 1218.19
  4935.3 1219.41  4943.9 1217.05  4980.3 1212.41  5003.6 1211.34  5004.1 1210.84
  5017.3 1211.34  5024.7 1213.95  5033.2 1213.74  5039.0 1215.91  5045.7 1214.76
  5054.4 1216.27  5097.0 1216.15  5112.4 1221.18  5118.3 1219.97  5127.8 1221.51
  5133.7 1220.55  5149.1 1223.38  5232.9 1226.30  5249.6 1226.59  5265.0 1229.59
  5286.3 1229.64  5322.9 1235.26  5344.2 1234.86  5359.6 1237.09  5409.9 1239.64
#Mann=5,-1,0
  4760.1    0.05       0  5003.6    0.05       0  5017.3    0.05       0
  5024.7    0.12       0  5232.9    0.05       0
Bank Sta=5003.6,5017.3
Exp/Cntr=0.3,0.1

Type RM Length L Ch R = 1,16500,500,500,500
BEGIN DESCRIPTION:
NORTH WILLOW CREEK 33.0
END DESCRIPTION:
XS GIS Cut Line= 3
      2752705.66     10257103.07      2752471.38     10256717.11
      2752405.67     10256503.07
#Sta/Elev= 30
  4548.5 1235.87  4733.7 1229.27  4752.0 1228.97  4767.5 1227.12  4773.3 1227.73
  4788.8 1225.35  4831.5 1222.49  4862.4 1219.28  4926.5 1216.96  4957.4 1214.76
  4992.5 1208.15  4993.0 1207.65  5006.3 1208.15  5014.6 1209.55  5033.4 1210.78
  5066.1 1209.62  5071.4 1210.35  5077.4 1214.36  5092.7 1218.61  5104.1 1222.90
  5109.3 1222.98  5136.8 1229.29  5142.0 1228.51  5150.6 1230.83  5161.1 1231.36
  5169.5 1233.15  5174.8 1231.99  5202.3 1235.68  5207.5 1234.75  5223.9 1237.33
#Mann=5,-1,0
  4548.5    0.12       0  4733.7    0.05       0  4992.5    0.05       0
  5006.3    0.05       0  5092.7    0.12       0
Bank Sta=4992.5,5006.3
Exp/Cntr=0.3,0.1

Type RM Length L Ch R = 1,16000,500,500,500
BEGIN DESCRIPTION:
NORTH WILLOW CREEK 32.0
END DESCRIPTION:
XS GIS Cut Line= 3
      2752855.68     10257053.13      2752909.25     10256779.83
      2753005.70     10256453.07
#Sta/Elev= 30
  4721.5 1233.51  4731.7 1233.49  4747.3 1231.15  4772.5 1229.97  4798.7 1227.29
  4803.8 1228.03  4850.2 1223.06  4855.3 1223.30  4874.4 1221.09  4921.6 1217.70
  4957.1 1214.09  4976.3 1210.85  4986.5 1207.17  4988.9 1204.80  4989.4 1204.30
  5002.7 1204.80  5017.4 1206.01  5041.9 1205.25  5048.7 1207.25  5069.6 1208.92
  5080.5 1210.81  5173.8 1217.47  5185.6 1219.40  5194.7 1219.43  5218.9 1221.52
  5257.4 1227.57  5285.7 1230.58  5309.4 1232.86  5337.9 1233.96  5340.7 1233.96
#Mann=7,-1,0
  4721.5    0.05       0  4921.6    0.12       0  4957.1    0.05       0
  4988.9    0.05       0  5002.7    0.05       0  5285.7    0.12       0
  5337.9    0.05       0
Bank Sta=4988.9,5002.7
Exp/Cntr=0.3,0.1

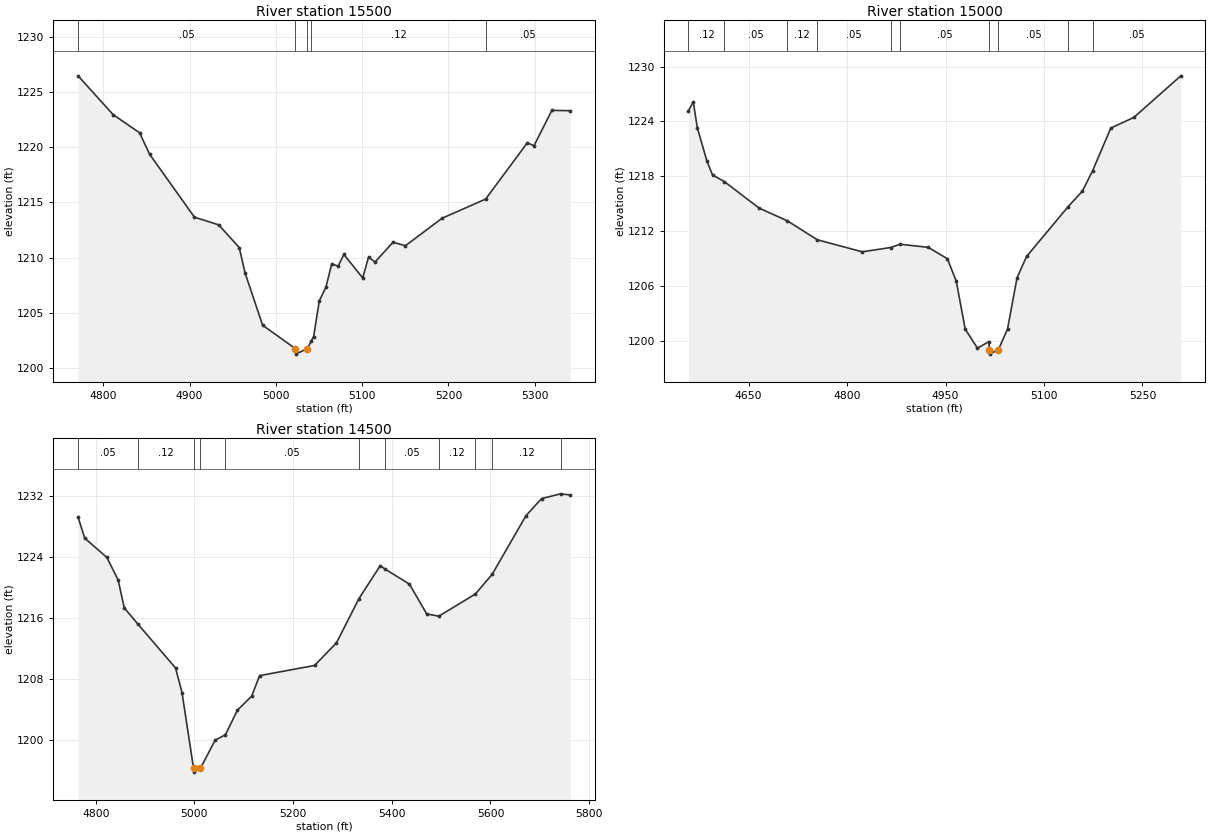
Type RM Length L Ch R = 1,15500,500,500,500
BEGIN DESCRIPTION:
NORTH WILLOW CREEK 31.0
END DESCRIPTION:
XS GIS Cut Line= 3
      2753355.68     10257103.12      2753399.00     10256878.05
      2753655.69     10256653.11
#Sta/Elev= 30
  4770.8 1226.47  4811.5 1222.95  4842.1 1221.31  4853.8 1219.36  4905.7 1213.66
  4933.7 1212.97  4957.6 1210.91  4964.3 1208.62  4984.7 1203.87  5022.6 1201.75
  5023.1 1201.25  5036.5 1201.75  5041.3 1202.47  5043.8 1202.84  5050.4 1206.09
  5058.0 1207.30  5064.7 1209.41  5072.2 1209.23  5078.9 1210.28  5100.7 1208.15
  5107.4 1210.04  5115.0 1209.60  5135.8 1211.39  5150.1 1211.07  5192.8 1213.57
  5243.1 1215.30  5291.5 1220.41  5299.1 1220.13  5319.9 1223.34  5341.3 1223.31
#Mann=5,-1,0
  4770.8    0.05       0  5022.6    0.05       0  5036.5    0.05       0
  5041.3    0.12       0  5243.1    0.05       0
Bank Sta=5022.6,5036.5
Exp/Cntr=0.3,0.1

Type RM Length L Ch R = 1,15000,500,500,500
BEGIN DESCRIPTION:
NORTH WILLOW CREEK 30.0
END DESCRIPTION:
XS GIS Cut Line= 3
      2753505.69     10257303.11      2753862.93     10257043.35
      2754105.67     10256853.12
#Sta/Elev= 30
  4558.3 1225.17  4565.6 1226.16  4571.8 1223.30  4586.5 1219.64  4595.0 1218.14
  4613.0 1217.41  4666.1 1214.50  4708.6 1213.13  4754.5 1211.04  4823.0 1209.72
  4866.3 1210.19  4880.7 1210.55  4923.5 1210.21  4952.8 1208.96  4966.3 1206.50
  4979.9 1201.26  4998.6 1199.16  5016.2 1199.89  5016.7 1199.01  5017.2 1198.51
  5030.6 1199.01  5044.4 1201.26  5058.9 1206.87  5073.4 1209.21  5136.9 1214.68
  5158.4 1216.36  5173.9 1218.58  5201.7 1223.27  5237.0 1224.45  5308.4 1229.00
#Mann=10,-1,0
  4558.3    0.12       0  4613.0    0.05       0  4708.6    0.12       0
  4754.5    0.05       0  4866.3    0.12       0  4880.7    0.05       0
  5016.7    0.05       0  5030.6    0.05       0  5136.9    0.12       0
  5173.9    0.05       0
Bank Sta=5016.7,5030.6
Exp/Cntr=0.3,0.1

Type RM Length L Ch R = 1,14500,500,500,500
BEGIN DESCRIPTION:
NORTH WILLOW CREEK 29.0
END DESCRIPTION:
XS GIS Cut Line= 3
      2753705.68     10257603.11      2753907.13     10257480.56
      2754255.70     10256803.07
#Sta/Elev= 30
  4764.2 1229.25  4777.8 1226.48  4822.7 1223.94  4845.5 1220.97  4857.8 1217.32
  4885.6 1215.17  4961.8 1209.41  4974.9 1206.18  4998.3 1196.21  4998.8 1195.71
  5012.2 1196.21  5042.1 1199.91  5063.0 1200.63  5087.1 1203.85  5116.1 1205.70
  5132.1 1208.40  5243.6 1209.74  5287.9 1212.71  5333.4 1218.52  5376.6 1222.86
  5387.2 1222.38  5435.7 1220.44  5470.9 1216.51  5495.3 1216.22  5569.2 1219.12
  5603.4 1221.72  5671.9 1229.43  5703.6 1231.69  5742.5 1232.31  5761.9 1232.16
#Mann=11,-1,0
  4764.2    0.05       0  4885.6    0.12       0  4998.3    0.07       0
  5012.2    0.12       0  5063.0    0.05       0  5333.4    0.12       0
  5387.2    0.05       0  5495.3    0.12       0  5569.2    0.05       0
  5603.4    0.12       0  5742.5    0.05       0
Bank Sta=4998.3,5012.2
Exp/Cntr=0.3,0.1