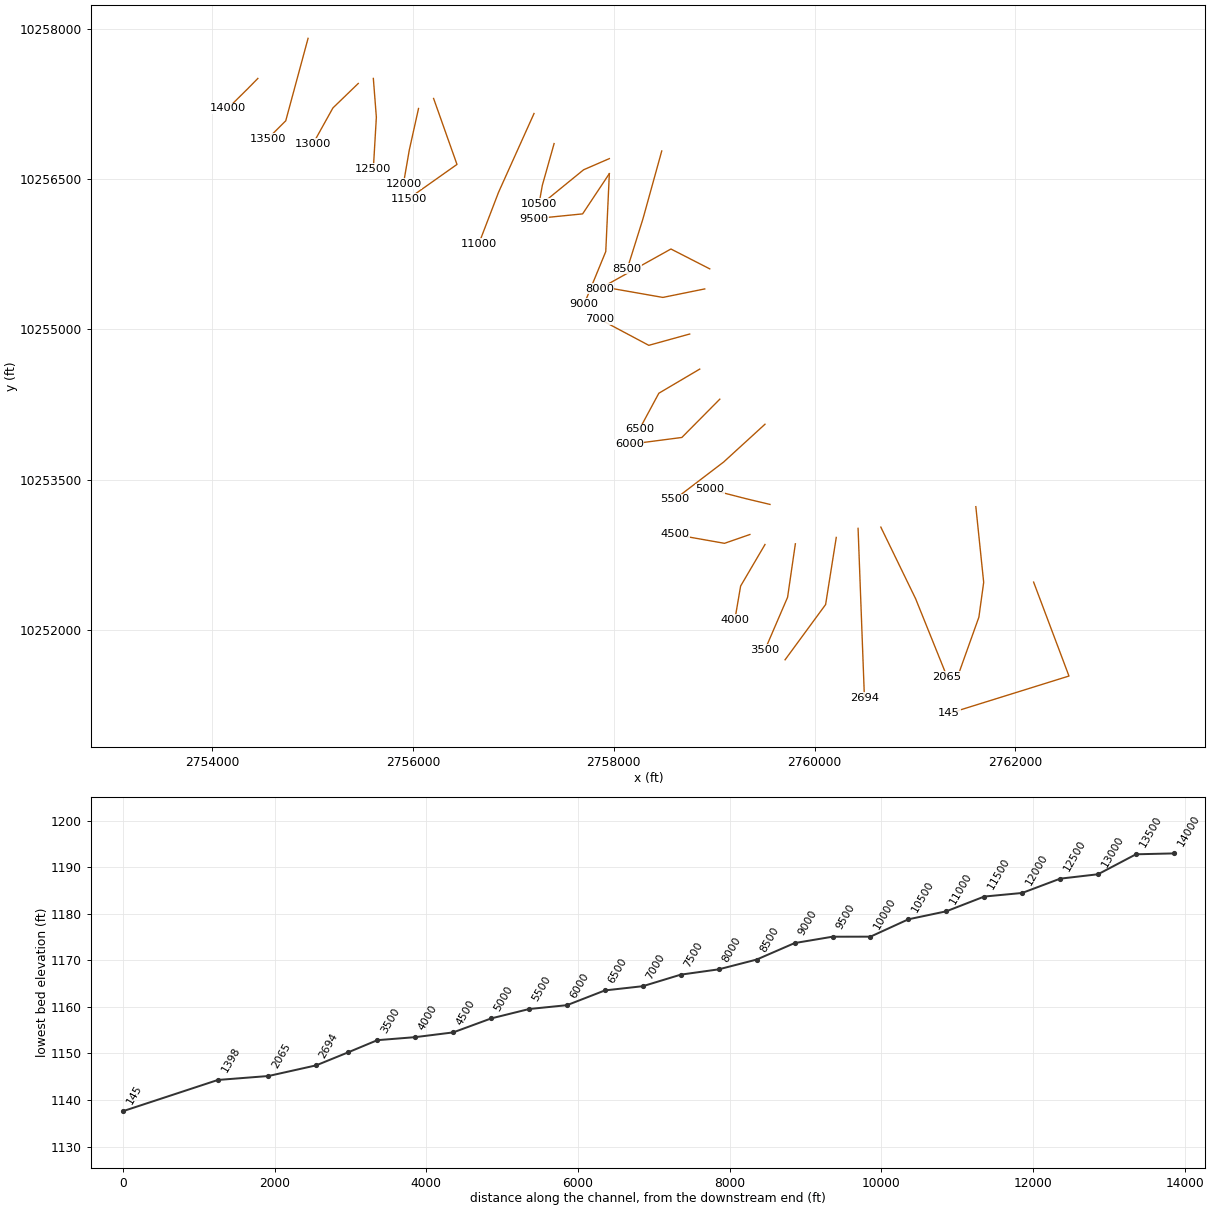
HEC-RAS study NORTH WILLOW CREEK.prj: NORTH WILLOW CREEK Base Level Engineering

--- NORTH WILLOW CREEK.g01 (geometry) --- (continued)

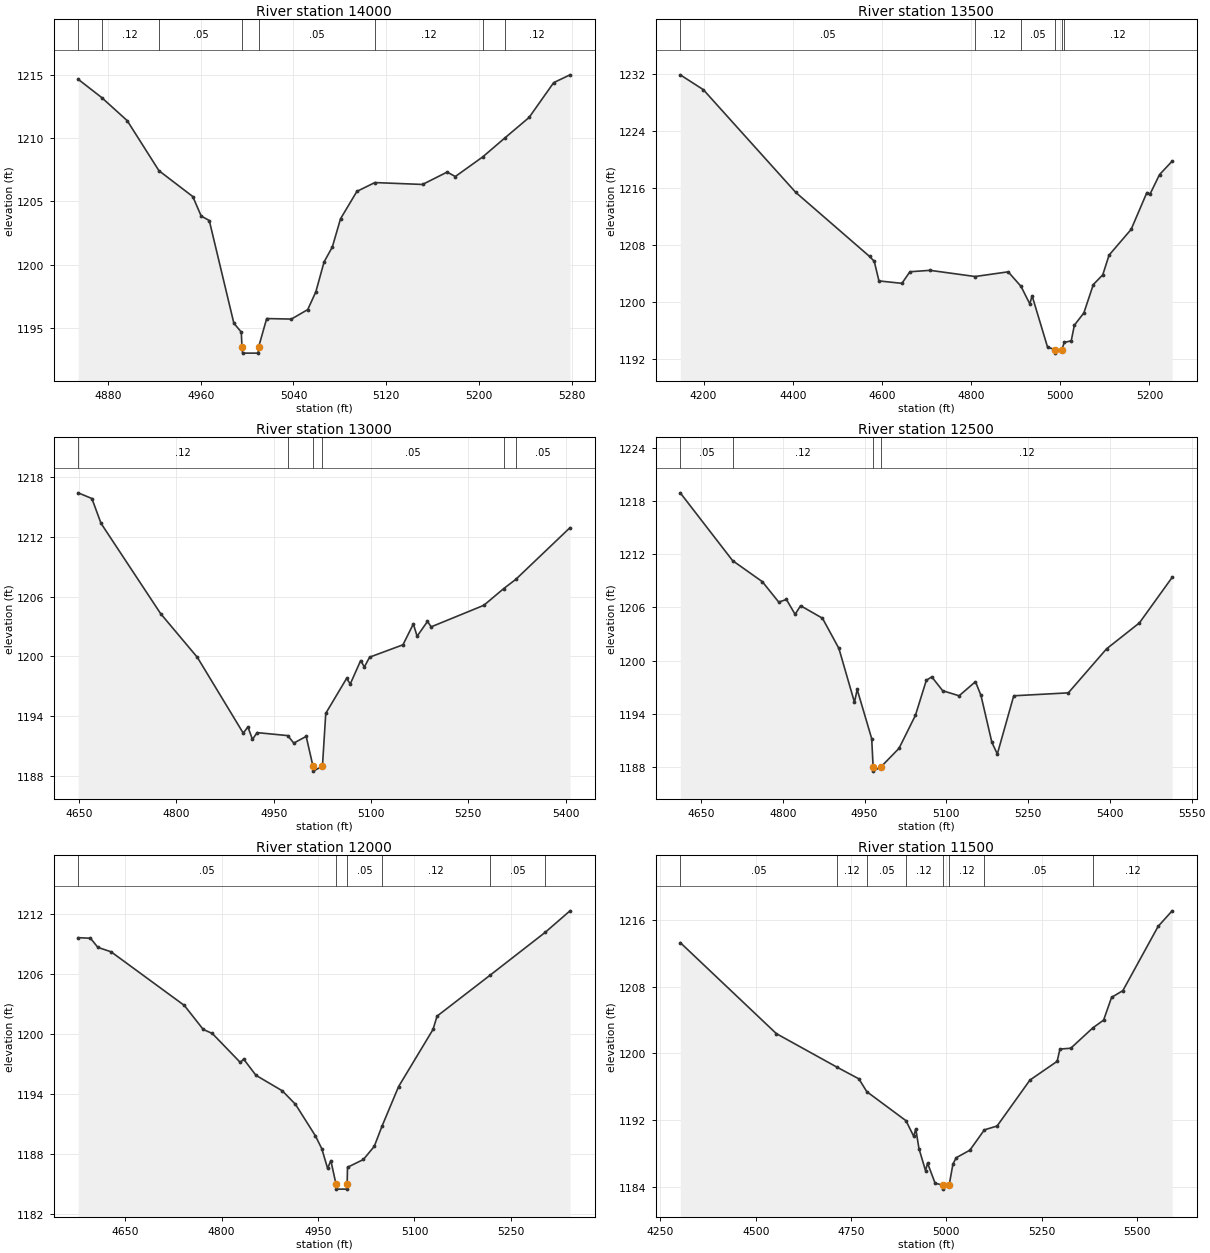
Type RM Length L Ch R = 1,14000,500,500,500
BEGIN DESCRIPTION:
NORTH WILLOW CREEK 28.0
END DESCRIPTION:
XS GIS Cut Line= 3
      2754455.67     10257503.09      2754353.63     10257399.09
      2754155.72     10257203.15
#Sta/Elev= 30
  4854.3 1214.69  4874.6 1213.24  4896.6 1211.41  4924.0 1207.44  4953.2 1205.39
  4960.4 1203.85  4967.4 1203.49  4988.6 1195.35  4995.0 1194.65  4995.6 1193.48
  4996.1 1192.98  5009.5 1192.98  5010.0 1193.48  5016.9 1195.72  5038.2 1195.68
  5052.3 1196.43  5059.3 1197.84  5066.4 1200.21  5073.5 1201.39  5080.6 1203.63
  5094.7 1205.80  5110.2 1206.50  5151.3 1206.35  5172.5 1207.33  5179.6 1206.98
  5203.3 1208.54  5222.1 1210.02  5243.2 1211.66  5264.4 1214.42  5278.5 1215.04
#Mann=8,-1,0
  4854.3    0.05       0  4874.6    0.12       0  4924.0    0.05       0
  4995.6    0.05       0  5010.0    0.05       0  5110.2    0.12       0
  5203.3    0.05       0  5222.1    0.12       0
Bank Sta=4995.6,5010
Exp/Cntr=0.3,0.1

Type RM Length L Ch R = 1,13500,500,500,500
BEGIN DESCRIPTION:
NORTH WILLOW CREEK 27.0
END DESCRIPTION:
XS GIS Cut Line= 3
      2754955.68     10257903.11      2754733.34     10257080.22
      2754555.65     10256903.08
#Sta/Elev= 30
  4147.6 1231.95  4199.4 1229.86  4406.6 1215.41  4572.3 1206.39  4582.7 1205.71
  4593.3 1202.95  4644.8 1202.61  4662.7 1204.24  4707.8 1204.44  4808.9 1203.57
  4883.1 1204.23  4911.9 1202.19  4931.6 1199.72  4936.8 1200.86  4971.5 1193.62
  4988.7 1193.29  4989.2 1192.79  5003.2 1193.29  5009.1 1194.29  5024.6 1194.53
  5031.6 1196.72  5052.9 1198.45  5074.1 1202.44  5095.3 1203.81  5109.4 1206.58
  5158.9 1210.20  5194.3 1215.39  5201.4 1215.18  5222.6 1217.91  5250.9 1219.80
#Mann=6,-1,0
  4147.6    0.05       0  4808.9    0.12       0  4911.9    0.05       0
  4988.7    0.05       0  5003.2    0.05       0  5009.1    0.12       0
Bank Sta=4988.7,5003.2
Exp/Cntr=0.3,0.1

Type RM Length L Ch R = 1,13000,500,500,500
BEGIN DESCRIPTION:
NORTH WILLOW CREEK 26.0
END DESCRIPTION:
XS GIS Cut Line= 3
      2755455.66     10257453.09      2755203.09     10257208.64
      2755005.66     10256853.07
#Sta/Elev= 30
  4648.5 1216.39  4669.7 1215.82  4683.8 1213.33  4775.7 1204.28  4832.3 1199.90
  4903.0 1192.31  4910.2 1192.93  4917.2 1191.68  4924.4 1192.36  4971.6 1192.06
  4980.9 1191.31  5000.0 1191.98  5010.5 1189.00  5011.0 1188.50  5025.1 1189.00
  5030.2 1194.29  5062.3 1197.79  5068.0 1197.24  5084.0 1199.58  5089.7 1198.94
  5097.8 1199.92  5149.2 1201.16  5165.2 1203.25  5171.0 1202.02  5187.0 1203.50
  5192.7 1202.96  5273.9 1205.12  5304.6 1206.80  5323.0 1207.71  5406.7 1212.90
#Mann=6,-1,0
  4648.5    0.12       0  4971.6    0.05       0  5010.5    0.05       0
  5025.1    0.05       0  5304.6    0.12       0  5323.0    0.05       0
Bank Sta=5010.5,5025.1
Exp/Cntr=0.3,0.1

Type RM Length L Ch R = 1,12500,500,500,500
BEGIN DESCRIPTION:
NORTH WILLOW CREEK 25.0
END DESCRIPTION:
XS GIS Cut Line= 3
      2755605.68     10257503.12      2755635.70     10257116.39
      2755605.68     10256603.06
#Sta/Elev= 30
  4612.1 1218.91  4708.1 1211.27  4762.6 1208.90  4792.7 1206.60  4806.8 1206.89
  4822.7 1205.22  4832.8 1206.19  4872.9 1204.78  4903.0 1201.38  4931.6 1195.31
  4936.6 1196.75  4963.2 1191.21  4965.8 1188.05  4966.3 1187.55  4980.5 1188.05
  5013.3 1190.12  5043.4 1193.84  5063.4 1197.79  5073.4 1198.17  5093.4 1196.61
  5123.5 1196.04  5153.5 1197.63  5163.6 1196.08  5183.6 1190.79  5193.6 1189.48
  5223.7 1196.04  5323.8 1196.37  5393.9 1201.33  5454.1 1204.25  5514.2 1209.38
#Mann=4,-1,0
  4612.1    0.05       0  4708.1    0.12       0  4965.8    0.07       0
  4980.5    0.12       0
Bank Sta=4965.8,4980.5
Exp/Cntr=0.3,0.1

Type RM Length L Ch R = 1,12000,500,500,500
BEGIN DESCRIPTION:
NORTH WILLOW CREEK 24.0
END DESCRIPTION:
XS GIS Cut Line= 3
      2756055.69     10257203.12      2755963.89     10256790.00
      2755905.68     10256453.09
#Sta/Elev= 30
  4576.8 1209.60  4596.0 1209.54  4607.5 1208.63  4628.0 1208.19  4742.0 1202.83
  4771.4 1200.43  4785.5 1200.03  4829.1 1197.13  4834.2 1197.47  4853.4 1195.85
  4894.4 1194.30  4914.9 1192.95  4945.6 1189.83  4955.8 1188.52  4964.8 1186.56
  4969.9 1187.33  4977.9 1184.98  4978.4 1184.48  4994.7 1184.48  4995.2 1184.98
  4995.8 1186.66  5020.5 1187.44  5037.4 1188.75  5049.4 1190.76  5075.3 1194.73
  5128.8 1200.43  5135.1 1201.76  5217.4 1205.84  5303.3 1210.13  5341.9 1212.28
#Mann=6,-1,0
  4576.8    0.05       0  4977.9    0.05       0  4995.2    0.05       0
  5049.4    0.12       0  5217.4    0.05       0  5303.3    0.12       0
Bank Sta=4977.9,4995.2
Exp/Cntr=0.3,0.1

Type RM Length L Ch R = 1,11500,500,500,500
BEGIN DESCRIPTION:
NORTH WILLOW CREEK 23.0
END DESCRIPTION:
XS GIS Cut Line= 3
      2756205.69     10257303.11      2756438.55     10256645.20
      2755955.65     10256303.09
#Sta/Elev= 30
  4302.1 1213.28  4554.1 1202.36  4713.8 1198.32  4770.4 1196.94  4791.2 1195.40
  4893.9 1191.92  4914.3 1190.04  4919.6 1190.95  4928.0 1188.57  4945.2 1185.93
  4950.5 1186.83  4970.4 1184.41  4989.8 1184.21  4990.3 1183.71  5007.2 1184.21
  5017.1 1186.73  5025.7 1187.48  5061.4 1188.38  5099.5 1190.82  5132.8 1191.28
  5218.9 1196.79  5290.3 1199.04  5297.6 1200.51  5326.0 1200.61  5383.8 1203.05
  5412.1 1203.98  5433.0 1206.71  5462.6 1207.52  5555.0 1215.22  5591.8 1217.09
#Mann=8,-1,0
  4302.1    0.05       0  4713.8    0.12       0  4791.2    0.05       0
  4893.9    0.12       0  4989.8    0.07       0  5007.2    0.12       0
  5099.5    0.05       0  5383.8    0.12       0
Bank Sta=4989.8,5007.2
Exp/Cntr=0.3,0.1

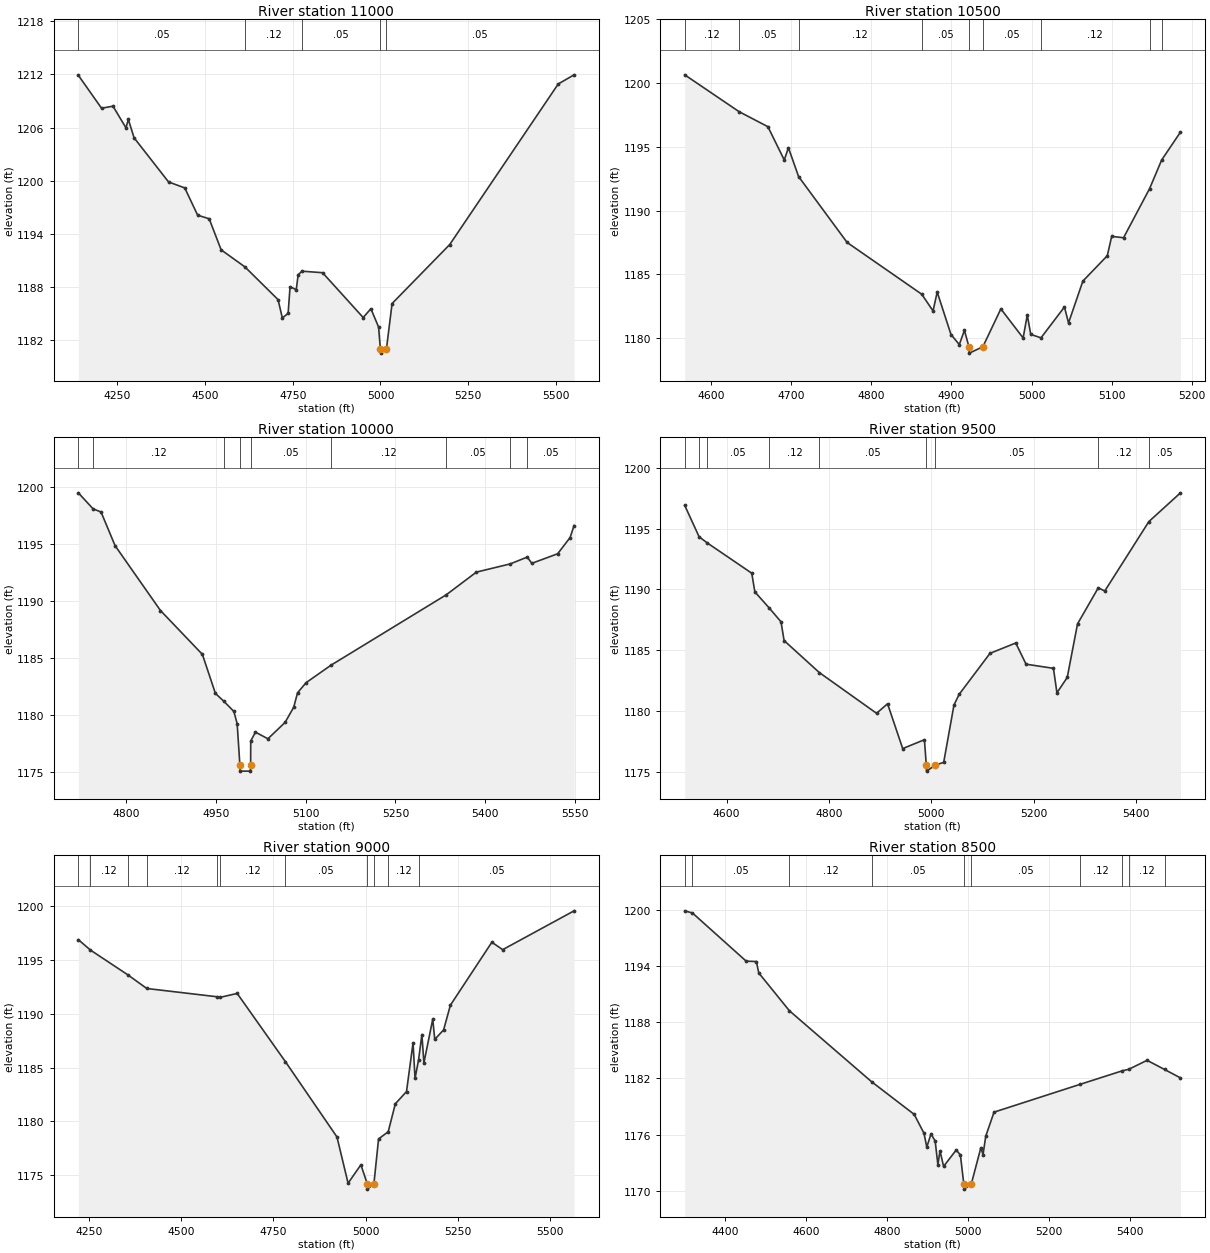
Type RM Length L Ch R = 1,11000,500,500,500
BEGIN DESCRIPTION:
NORTH WILLOW CREEK 22.0
END DESCRIPTION:
XS GIS Cut Line= 3
      2757205.69     10257153.12      2756852.86     10256368.17
      2756655.69     10255853.12
#Sta/Elev= 30
  4139.4 1211.91  4205.5 1208.19  4238.1 1208.42  4275.0 1205.98  4281.9 1206.92
  4298.2 1204.85  4396.3 1199.87  4442.6 1199.19  4479.3 1196.11  4512.1 1195.71
  4546.2 1192.20  4614.1 1190.27  4708.3 1186.58  4720.5 1184.51  4737.0 1185.03
  4742.5 1188.04  4760.1 1187.70  4765.6 1189.39  4776.4 1189.79  4835.1 1189.62
  4950.7 1184.56  4972.7 1185.55  4994.6 1183.49  4999.7 1181.04  5000.2 1180.54
  5017.1 1181.04  5033.1 1186.14  5197.3 1192.80  5506.4 1210.93  5551.5 1211.96
#Mann=5,-1,0
  4139.4    0.05       0  4614.1    0.12       0  4776.4    0.05       0
  4999.7    0.05       0  5017.1    0.05       0
Bank Sta=4999.7,5017.1
Exp/Cntr=0.3,0.1

Type RM Length L Ch R = 1,10500,500,500,500
BEGIN DESCRIPTION:
NORTH WILLOW CREEK 21.0
END DESCRIPTION:
XS GIS Cut Line= 3
      2757405.69     10256853.14      2757288.33     10256436.24
      2757255.69     10256253.13
#Sta/Elev= 30
  4566.9 1200.65  4634.8 1197.76  4670.8 1196.58  4691.2 1193.97  4696.4 1194.93
  4709.1 1192.67  4769.7 1187.50  4862.9 1183.44  4877.0 1182.13  4882.2 1183.61
  4899.4 1180.28  4909.8 1179.49  4916.2 1180.61  4921.8 1179.32  4922.3 1178.82
  4939.2 1179.32  4961.7 1182.29  4989.5 1180.01  4994.7 1181.81  4999.0 1180.29
  5011.8 1180.02  5041.1 1182.44  5046.2 1181.19  5064.1 1184.47  5094.6 1186.46
  5100.1 1187.98  5114.9 1187.87  5147.4 1191.72  5162.5 1193.97  5186.0 1196.16
#Mann=9,-1,0
  4566.9    0.12       0  4634.8    0.05       0  4709.1    0.12       0
  4862.9    0.05       0  4921.8    0.05       0  4939.2    0.05       0
  5011.8    0.12       0  5147.4    0.05       0  5162.5    0.12       0
Bank Sta=4921.8,4939.2
Exp/Cntr=0.3,0.1

Type RM Length L Ch R = 1,10000,500,500,500
BEGIN DESCRIPTION:
NORTH WILLOW CREEK 20.0
END DESCRIPTION:
XS GIS Cut Line= 3
      2757955.71     10256703.12      2757699.29     10256591.65
      2757274.36     10256244.83
#Sta/Elev= 30
  4720.4 1199.52  4745.1 1198.11  4758.3 1197.84  4781.8 1194.88  4857.6 1189.19
  4927.6 1185.34  4949.4 1181.91  4963.5 1181.22  4980.2 1180.33  4985.7 1179.26
  4990.3 1175.59  4990.8 1175.09  5007.7 1175.09  5008.2 1175.59  5008.4 1177.74
  5016.3 1178.51  5037.1 1177.93  5065.8 1179.37  5080.2 1180.70  5086.6 1181.97
  5101.0 1182.86  5142.2 1184.38  5335.0 1190.57  5385.3 1192.56  5441.8 1193.28
  5470.3 1193.88  5477.9 1193.33  5521.0 1194.17  5541.8 1195.59  5548.5 1196.65
#Mann=9,-1,0
  4720.4    0.05       0  4745.1    0.12       0  4963.5    0.05       0
  4990.3    0.03       0  5008.2    0.05       0  5142.2    0.12       0
  5335.0    0.05       0  5441.8    0.12       0  5470.3    0.05       0
Bank Sta=4990.3,5008.2
Exp/Cntr=0.3,0.1

Type RM Length L Ch R = 1,9500,500,500,500
BEGIN DESCRIPTION:
NORTH WILLOW CREEK 19.0
END DESCRIPTION:
XS GIS Cut Line= 3
      2757955.71     10256553.15      2757689.54     10256151.78
      2757205.68     10256103.11
#Sta/Elev= 30
  4518.4 1196.90  4546.5 1194.32  4562.3 1193.82  4649.3 1191.33  4655.3 1189.80
  4683.7 1188.46  4706.4 1187.34  4712.4 1185.80  4781.3 1183.17  4892.9 1179.83
  4914.4 1180.61  4944.0 1176.93  4986.4 1177.66  4990.0 1175.58  4990.5 1175.08
  5008.0 1175.58  5024.0 1175.80  5044.1 1180.51  5054.1 1181.38  5114.4 1184.75
  5164.7 1185.60  5184.8 1183.86  5238.3 1183.52  5245.1 1181.51  5265.2 1182.77
  5285.3 1187.17  5325.8 1190.13  5338.5 1189.87  5424.6 1195.57  5486.3 1197.93
#Mann=9,-1,0
  4518.4    0.05       0  4546.5    0.12       0  4562.3    0.05       0
  4683.7    0.12       0  4781.3    0.05       0  4990.0    0.03       0
  5008.0    0.05       0  5325.8    0.12       0  5424.6    0.05       0
Bank Sta=4990,5008
Exp/Cntr=0.3,0.1

Type RM Length L Ch R = 1,9000,500,500,500
BEGIN DESCRIPTION:
NORTH WILLOW CREEK 18.0
END DESCRIPTION:
XS GIS Cut Line= 3
      2757955.68     10256553.10      2757920.10     10255775.81
      2757705.67     10255253.08
#Sta/Elev= 30
  4221.9 1196.90  4254.8 1195.93  4356.0 1193.63  4407.4 1192.36  4598.2 1191.59
  4606.3 1191.54  4652.3 1191.90  4782.7 1185.57  4922.6 1178.56  4952.7 1174.26
  4987.4 1175.97  5004.7 1174.21  5005.2 1173.71  5022.7 1174.21  5035.3 1178.38
  5061.4 1179.04  5080.7 1181.64  5111.0 1182.78  5128.7 1187.31  5134.1 1184.00
  5143.7 1185.73  5152.7 1188.08  5158.1 1185.44  5182.1 1189.51  5187.5 1187.63
  5211.5 1188.51  5229.9 1190.81  5342.2 1196.66  5371.6 1195.97  5565.0 1199.58
#Mann=11,-1,0
  4221.9    0.05       0  4254.8    0.12       0  4356.0    0.05       0
  4407.4    0.12       0  4598.2    0.05       0  4606.3    0.12       0
  4782.7    0.05       0  5004.7    0.05       0  5022.7    0.05       0
  5061.4    0.12       0  5143.7    0.05       0
Bank Sta=5004.7,5022.7
Exp/Cntr=0.3,0.1

Type RM Length L Ch R = 1,8500,500,500,500
BEGIN DESCRIPTION:
NORTH WILLOW CREEK 17.0
END DESCRIPTION:
XS GIS Cut Line= 3
      2758477.64     10256779.41      2758291.08     10256104.31
      2758134.53     10255604.14
#Sta/Elev= 30
  4299.6 1199.92  4318.7 1199.69  4451.4 1194.54  4476.6 1194.50  4482.5 1193.28
  4558.1 1189.24  4761.2 1181.65  4866.4 1178.16  4890.6 1176.14  4897.5 1174.66
  4907.9 1176.07  4918.2 1175.31  4924.9 1172.78  4930.1 1174.27  4939.0 1172.60
  4970.1 1174.35  4980.5 1173.83  4989.0 1170.67  4989.5 1170.17  5007.1 1170.67
  5031.1 1174.60  5036.4 1173.86  5043.2 1175.84  5063.6 1178.40  5276.1 1181.37
  5380.5 1182.82  5396.4 1182.98  5441.6 1183.94  5484.8 1182.96  5524.1 1182.06
#Mann=10,-1,0
  4299.6    0.12       0  4318.7    0.05       0  4558.1    0.12       0
  4761.2    0.05       0  4989.0    0.03       0  5007.1    0.05       0
  5276.1    0.12       0  5380.5    0.05       0  5396.4    0.12       0
  5484.8    0.05       0
Bank Sta=4989,5007.1
Exp/Cntr=0.3,0.1

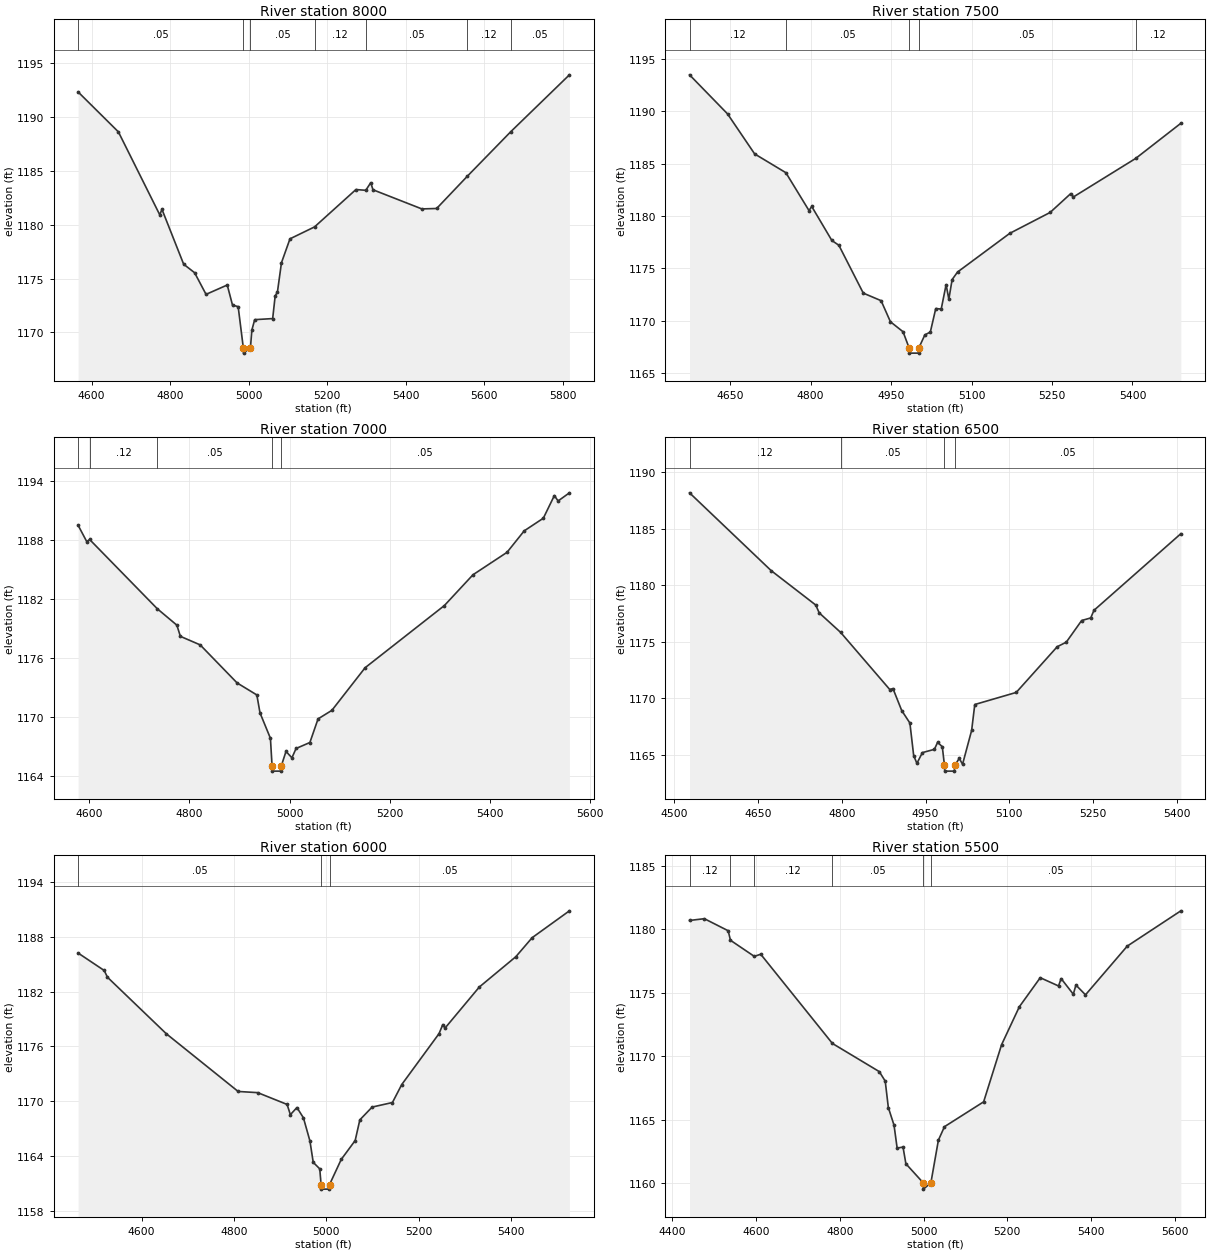
Type RM Length L Ch R = 1,8000,500,500,500
BEGIN DESCRIPTION:
NORTH WILLOW CREEK 16.0
END DESCRIPTION:
XS GIS Cut Line= 3
      2758955.64     10255603.13      2758569.13     10255801.41
      2757855.68     10255403.11
#Sta/Elev= 30
  4565.6 1192.34  4668.2 1188.63  4773.6 1180.92  4779.2 1181.43  4834.5 1176.33
  4862.4 1175.54  4891.5 1173.53  4945.5 1174.40  4958.9 1172.53  4973.3 1172.39
  4986.4 1168.57  4986.9 1168.07  5004.6 1168.57  5008.2 1170.21  5015.4 1171.18
  5061.2 1171.28  5067.6 1173.39  5073.3 1173.74  5083.6 1176.47  5105.3 1178.69
  5167.9 1179.80  5273.3 1183.27  5298.4 1183.20  5311.0 1183.91  5316.7 1183.25
  5441.2 1181.47  5478.9 1181.51  5557.4 1184.52  5667.8 1188.65  5817.1 1193.93
#Mann=7,-1,0
  4565.6    0.05       0  4986.4    0.05       0  5004.6    0.05       0
  5167.9    0.12       0  5298.4    0.05       0  5557.4    0.12       0
  5667.8    0.05       0
Bank Sta=4986.4,5004.6
Exp/Cntr=0.3,0.1

Type RM Length L Ch R = 1,7500,500,500,500
BEGIN DESCRIPTION:
NORTH WILLOW CREEK 15.0
END DESCRIPTION:
XS GIS Cut Line= 3
      2758905.68     10255403.11      2758488.51     10255318.32
      2758005.70     10255403.11
#Sta/Elev= 30
  4574.3 1193.46  4645.1 1189.74  4695.7 1185.92  4753.9 1184.13  4797.0 1180.52
  4802.1 1180.91  4839.6 1177.67  4852.7 1177.21  4898.2 1172.65  4931.4 1171.93
  4948.8 1169.92  4972.3 1168.97  4983.6 1167.43  4984.1 1166.93  5001.3 1166.93
  5001.8 1167.43  5013.0 1168.67  5023.2 1168.94  5033.3 1171.18  5043.5 1171.13
  5052.6 1173.46  5057.7 1172.07  5063.8 1173.94  5073.9 1174.66  5171.3 1178.35
  5246.5 1180.34  5285.0 1182.14  5290.0 1181.82  5406.0 1185.49  5490.2 1188.84
#Mann=5,-1,0
  4574.3    0.12       0  4753.9    0.05       0  4983.6    0.03       0
  5001.8    0.05       0  5406.0    0.12       0
Bank Sta=4983.6,5001.8
Exp/Cntr=0.3,0.1

Type RM Length L Ch R = 1,7000,500,500,500
BEGIN DESCRIPTION:
NORTH WILLOW CREEK 14.0
END DESCRIPTION:
XS GIS Cut Line= 3
      2758755.70     10254953.12      2758348.64     10254840.33
      2757855.70     10255103.10
#Sta/Elev= 30
  4577.6 1189.53  4594.8 1187.87  4600.6 1188.08  4735.8 1181.01  4774.8 1179.34
  4781.8 1178.20  4821.3 1177.33  4895.0 1173.45  4934.5 1172.22  4940.8 1170.39
  4961.6 1167.80  4964.9 1164.95  4965.4 1164.45  4982.6 1164.45  4983.1 1164.95
  4992.7 1166.46  5004.5 1165.81  5012.8 1166.76  5040.4 1167.37  5056.7 1169.78
  5084.3 1170.65  5150.7 1175.00  5308.9 1181.34  5366.0 1184.48  5434.0 1186.77
  5468.3 1188.96  5506.5 1190.25  5528.5 1192.56  5536.0 1192.01  5558.6 1192.84
#Mann=5,-1,0
  4577.6    0.05       0  4600.6    0.12       0  4735.8    0.05       0
  4964.9    0.03       0  4983.1    0.05       0
Bank Sta=4964.9,4983.1
Exp/Cntr=0.3,0.1

Type RM Length L Ch R = 1,6500,500,500,500
BEGIN DESCRIPTION:
NORTH WILLOW CREEK 13.0
END DESCRIPTION:
XS GIS Cut Line= 3
      2758855.71     10254603.12      2758448.58     10254362.34
      2758255.70     10254003.15
#Sta/Elev= 30
  4527.0 1188.19  4673.3 1181.30  4753.3 1178.25  4759.4 1177.56  4797.8 1175.83
  4885.9 1170.77  4891.7 1170.85  4907.3 1168.91  4922.0 1167.80  4928.8 1164.91
  4934.6 1164.23  4944.4 1165.18  4965.9 1165.47  4971.7 1166.09  4980.1 1165.70
  4984.0 1164.04  4984.5 1163.54  5001.8 1163.54  5002.3 1164.04  5010.5 1164.67
  5016.4 1164.15  5032.7 1167.15  5038.3 1169.44  5112.6 1170.51  5186.1 1174.56
  5202.3 1174.96  5229.9 1176.88  5246.2 1177.11  5251.9 1177.78  5407.7 1184.57
#Mann=4,-1,0
  4527.0    0.12       0  4797.8    0.05       0  4984.0    0.05       0
  5002.3    0.05       0
Bank Sta=4984,5002.3
Exp/Cntr=0.3,0.1

Type RM Length L Ch R = 1,6000,500,500,500
BEGIN DESCRIPTION:
NORTH WILLOW CREEK 12.0
END DESCRIPTION:
XS GIS Cut Line= 3
      2759055.67     10254303.10      2758677.69     10253921.09
      2758155.70     10253853.11
#Sta/Elev= 30
  4462.6 1186.21  4519.1 1184.30  4526.2 1183.56  4653.5 1177.38  4809.1 1171.06
  4851.5 1170.93  4915.1 1169.64  4922.2 1168.52  4936.4 1169.30  4950.5 1168.17
  4964.6 1165.63  4971.7 1163.30  4985.8 1162.59  4988.7 1160.87  4989.2 1160.37
  5006.5 1160.37  5007.0 1160.87  5032.3 1163.62  5062.5 1165.69  5072.6 1167.95
  5099.2 1169.35  5143.2 1169.85  5163.4 1171.82  5244.1 1177.39  5252.2 1178.38
  5257.3 1178.01  5331.3 1182.49  5410.4 1185.81  5445.7 1187.89  5526.4 1190.83
#Mann=3,-1,0
  4462.6    0.05       0  4988.7    0.03       0  5007.0    0.05       0
Bank Sta=4988.7,5007
Exp/Cntr=0.3,0.1

Type RM Length L Ch R = 1,5500,500,500,500
BEGIN DESCRIPTION:
NORTH WILLOW CREEK 11.0
END DESCRIPTION:
XS GIS Cut Line= 3
      2759505.67     10254053.10      2759093.67     10253675.89
      2758605.66     10253303.10
#Sta/Elev= 30
  4441.4 1180.71  4476.8 1180.85  4533.6 1179.90  4539.1 1179.15  4596.0 1177.88
  4611.3 1178.05  4782.4 1171.02  4894.3 1168.80  4908.5 1168.05  4915.9 1165.97
  4929.5 1164.58  4936.9 1162.78  4951.0 1162.85  4957.8 1161.54  4999.1 1160.04
  4999.6 1159.54  5017.5 1160.04  5035.4 1163.40  5049.9 1164.46  5143.4 1166.42
  5186.2 1170.92  5228.6 1173.91  5278.5 1176.20  5322.1 1175.55  5328.4 1176.13
  5357.4 1174.90  5363.7 1175.62  5386.5 1174.85  5486.2 1178.69  5614.1 1181.47
#Mann=6,-1,0
  4441.4    0.12       0  4539.1    0.05       0  4596.0    0.12       0
  4782.4    0.05       0  4999.1    0.05       0  5017.5    0.05       0
Bank Sta=4999.1,5017.5
Exp/Cntr=0.3,0.1

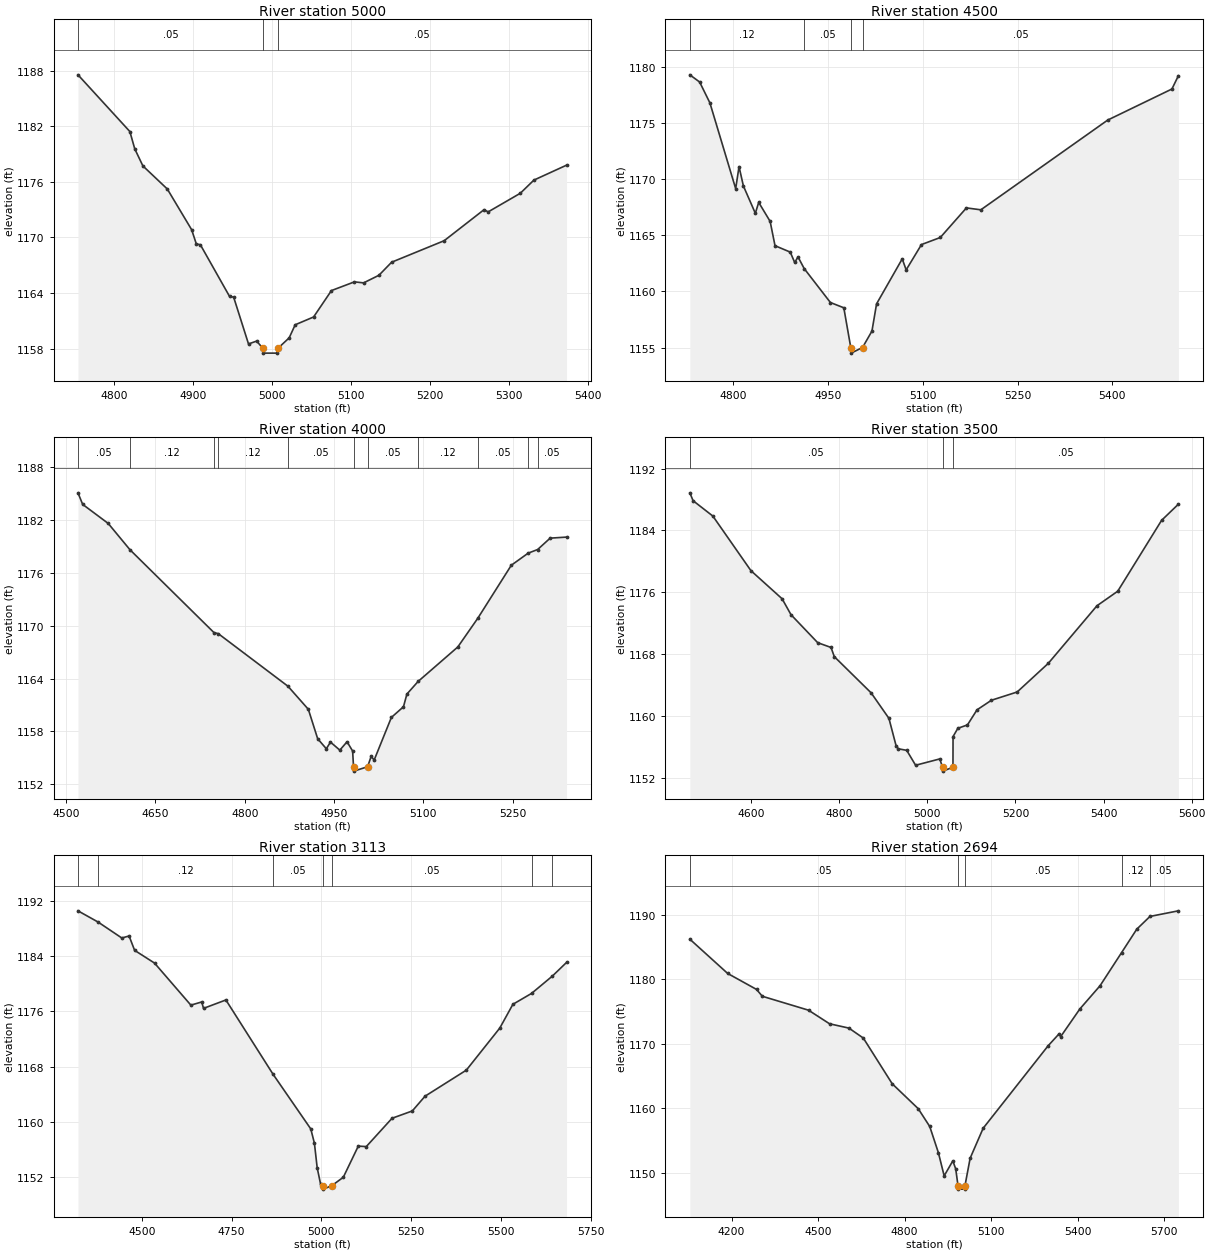
Type RM Length L Ch R = 1,5000,500,500,500
BEGIN DESCRIPTION:
NORTH WILLOW CREEK 10.0
END DESCRIPTION:
XS GIS Cut Line= 3
      2759555.65     10253253.12      2759316.77     10253310.17
      2758955.64     10253403.12
#Sta/Elev= 30
  4754.4 1187.55  4820.1 1181.43  4826.3 1179.56  4836.6 1177.72  4867.5 1175.23
  4898.3 1170.84  4904.2 1169.31  4909.4 1169.21  4946.3 1163.64  4951.5 1163.56
  4970.3 1158.51  4980.6 1158.82  4988.7 1158.02  4989.2 1157.52  5006.8 1157.52
  5007.3 1158.02  5021.8 1159.17  5029.4 1160.58  5052.7 1161.42  5075.3 1164.27
  5104.4 1165.21  5116.0 1165.10  5135.4 1165.92  5151.5 1167.33  5218.0 1169.65
  5268.5 1173.00  5273.7 1172.76  5314.4 1174.77  5331.6 1176.19  5372.9 1177.80
#Mann=3,-1,0
  4754.4    0.05       0  4988.7    0.05       0  5007.3    0.05       0
Bank Sta=4988.7,5007.3
Exp/Cntr=0.3,0.1

Type RM Length L Ch R = 1,4500,500,500,500
BEGIN DESCRIPTION:
NORTH WILLOW CREEK 9.0
END DESCRIPTION:
XS GIS Cut Line= 3
      2759355.66     10252953.10      2759102.23     10252865.04
      2758605.68     10252953.11
#Sta/Elev= 30
  4731.7 1179.26  4747.2 1178.62  4763.4 1176.77  4804.2 1169.14  4809.5 1171.10
  4816.4 1169.38  4835.3 1166.95  4840.6 1167.92  4858.7 1166.23  4866.4 1164.07
  4890.5 1163.50  4897.5 1162.58  4902.8 1163.07  4912.5 1162.04  4954.0 1159.02
  4975.2 1158.55  4986.2 1155.02  4986.7 1154.52  5004.8 1155.02  5019.7 1156.48
  5027.0 1158.90  5067.6 1162.90  5073.8 1161.92  5098.0 1164.17  5127.8 1164.80
  5169.1 1167.43  5191.9 1167.26  5392.6 1175.24  5494.1 1178.00  5504.3 1179.18
#Mann=4,-1,0
  4731.7    0.12       0  4912.5    0.05       0  4986.2    0.05       0
  5004.8    0.05       0
Bank Sta=4986.2,5004.8
Exp/Cntr=0.3,0.1

Type RM Length L Ch R = 1,4000,500,500,500
BEGIN DESCRIPTION:
NORTH WILLOW CREEK 8.0
END DESCRIPTION:
XS GIS Cut Line= 3
      2759505.69     10252853.12      2759263.02     10252438.87
      2759205.69     10252103.13
#Sta/Elev= 30
  4519.9 1185.06  4527.8 1183.75  4570.7 1181.59  4607.2 1178.61  4748.2 1169.22
  4755.8 1169.08  4872.6 1163.13  4906.9 1160.51  4922.6 1157.17  4937.1 1156.04
  4944.1 1156.79  4959.8 1155.88  4971.9 1156.83  4981.3 1155.78  4982.8 1154.00
  4983.3 1153.50  5006.5 1154.00  5012.4 1155.17  5017.5 1154.76  5046.4 1159.59
  5066.7 1160.80  5072.5 1162.24  5091.3 1163.67  5158.0 1167.58  5191.7 1170.85
  5247.9 1176.85  5276.2 1178.22  5292.1 1178.63  5313.1 1179.92  5340.6 1180.04
#Mann=11,-1,0
  4519.9    0.05       0  4607.2    0.12       0  4748.2    0.05       0
  4755.8    0.12       0  4872.6    0.05       0  4982.8    0.03       0
  5006.5    0.05       0  5091.3    0.12       0  5191.7    0.05       0
  5276.2    0.12       0  5292.1    0.05       0
Bank Sta=4982.8,5006.5
Exp/Cntr=0.3,0.1

Type RM Length L Ch R = 1,3500,387,387,387
BEGIN DESCRIPTION:
NORTH WILLOW CREEK 7.0
END DESCRIPTION:
XS GIS Cut Line= 3
      2759808.13     10252860.40      2759730.64     10252326.70
      2759505.67     10251803.08
#Sta/Elev= 30
  4460.7 1188.86  4468.1 1187.84  4513.0 1185.85  4599.4 1178.79  4670.2 1175.15
  4690.4 1173.09  4751.0 1169.47  4781.3 1168.85  4788.6 1167.67  4872.3 1162.98
  4912.7 1159.68  4929.0 1156.13  4934.0 1155.74  4953.1 1155.54  4973.3 1153.61
  5028.2 1154.43  5034.4 1153.35  5034.9 1152.85  5058.1 1153.35  5058.3 1157.32
  5069.2 1158.39  5091.0 1158.83  5112.7 1160.78  5145.4 1162.02  5203.9 1163.09
  5274.6 1166.80  5385.1 1174.25  5432.2 1176.13  5531.8 1185.30  5569.9 1187.39
#Mann=3,-1,0
  4460.7    0.05       0  5034.4    0.05       0  5058.1    0.05       0
Bank Sta=5034.4,5058.1
Exp/Cntr=0.3,0.1

Type RM Length L Ch R = 1,3113,419,419,419
BEGIN DESCRIPTION:
NORTH WILLOW CREEK 6.0
END DESCRIPTION:
XS GIS Cut Line= 3
      2760215.42     10252923.74      2760109.25     10252254.00
      2759705.68     10251703.11
#Sta/Elev= 30
  4321.9 1190.59  4378.0 1188.96  4444.0 1186.65  4464.3 1186.94  4479.7 1184.86
  4535.2 1183.01  4636.4 1176.91  4666.6 1177.37  4671.7 1176.44  4734.0 1177.66
  4865.3 1166.89  4970.5 1158.95  4980.6 1156.88  4988.3 1153.32  4997.9 1150.92
  5005.2 1150.72  5005.7 1150.22  5029.0 1150.72  5061.1 1151.94  5102.8 1156.46
  5125.1 1156.39  5196.9 1160.50  5253.3 1161.56  5288.8 1163.70  5403.8 1167.48
  5497.0 1173.58  5533.5 1177.03  5585.5 1178.61  5643.2 1181.11  5682.9 1183.10
#Mann=7,-1,0
  4321.9    0.05       0  4378.0    0.12       0  4865.3    0.05       0
  5005.2    0.05       0  5029.0    0.05       0  5585.5    0.12       0
  5643.2    0.05       0
Bank Sta=5005.2,5029
Exp/Cntr=0.3,0.1

Type RM Length L Ch R = 1,2694,629,629,629
BEGIN DESCRIPTION:
Mapping XS 2dbafe59
END DESCRIPTION:
XS GIS Cut Line= 2
      2760432.64     10253014.24      2760496.00     10251321.72
#Sta/Elev= 30
  4055.2 1186.23  4186.4 1180.91  4286.5 1178.43  4306.5 1177.37  4466.6 1175.21
  4539.6 1173.10  4606.7 1172.43  4656.7 1170.88  4756.8 1163.79  4846.9 1159.93
  4886.9 1157.16  4916.9 1153.09  4936.9 1149.50  4967.0 1151.83  4977.0 1150.57
  4985.0 1147.94  4985.5 1147.44  5008.4 1147.44  5008.9 1147.94  5027.0 1152.24
  5072.1 1156.89  5297.2 1169.68  5335.9 1171.57  5340.9 1171.11  5407.3 1175.40
  5477.3 1179.00  5552.2 1184.16  5604.6 1187.78  5650.4 1189.76  5748.9 1190.63
#Mann=5,-1,0
  4055.2    0.05       0  4985.0    0.03       0  5008.9    0.05       0
  5552.2    0.12       0  5650.4    0.05       0
Bank Sta=4985,5008.9
Exp/Cntr=0.3,0.1

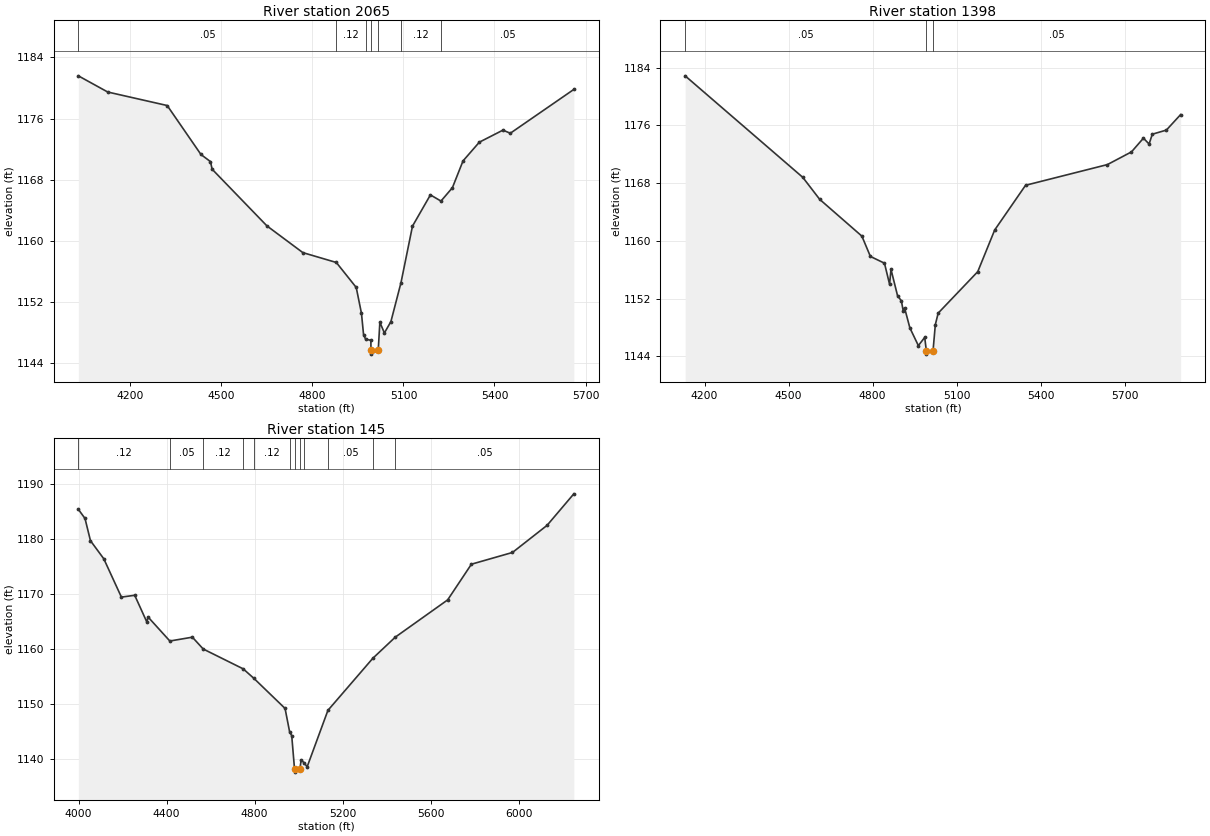
Type RM Length L Ch R = 1,2065,667,667,667
BEGIN DESCRIPTION:
Mapping XS 31cc99e8
END DESCRIPTION:
XS GIS Cut Line= 3
      2760659.11     10253026.79      2761006.32     10252310.68
      2761318.80     10251533.81
#Sta/Elev= 30
  4028.3 1181.59  4125.2 1179.47  4321.3 1177.70  4432.5 1171.29  4463.8 1170.36
  4469.4 1169.36  4650.0 1161.94  4768.4 1158.44  4878.7 1157.15  4944.3 1153.88
  4961.6 1150.48  4968.4 1147.72  4975.1 1147.11  4992.6 1146.96  4992.8 1145.65
  4993.3 1145.15  5016.8 1145.65  5022.2 1149.33  5037.1 1147.92  5058.6 1149.41
  5091.8 1154.50  5129.7 1161.91  5188.8 1166.00  5223.6 1165.19  5261.3 1166.94
  5296.3 1170.45  5350.0 1172.90  5427.9 1174.48  5452.1 1174.07  5661.5 1179.81
#Mann=7,-1,0
  4028.3    0.05       0  4878.7    0.12       0  4975.1    0.05       0
  4992.8    0.03       0  5016.8    0.05       0  5091.8    0.12       0
  5223.6    0.05       0
Bank Sta=4992.8,5016.8
Exp/Cntr=0.3,0.1

Type RM Length L Ch R = 1,1398,1253,1253,1253
BEGIN DESCRIPTION:
Mapping XS 3ed0b8ab
END DESCRIPTION:
XS GIS Cut Line= 4
      2761605.27     10253230.82      2761683.40     10252475.61
      2761635.66     10252128.38      2761414.37     10251507.90
#Sta/Elev= 30
  4130.7 1182.87  4550.6 1168.80  4611.0 1165.75  4761.6 1160.65  4791.9 1157.84
  4842.2 1156.90  4860.4 1153.98  4865.4 1156.05  4888.7 1152.42  4902.6 1151.67
  4908.8 1150.34  4913.8 1150.72  4932.8 1147.94  4963.1 1145.48  4985.8 1146.62
  4991.5 1144.80  4992.0 1144.30  5015.6 1144.80  5023.7 1148.39  5033.8 1149.98
  5175.1 1155.73  5235.5 1161.50  5345.7 1167.70  5637.9 1170.57  5723.8 1172.33
  5766.4 1174.23  5786.6 1173.42  5798.1 1174.78  5848.3 1175.35  5899.2 1177.50
#Mann=3,-1,0
  4130.7    0.05       0  4991.5    0.03       0  5015.6    0.05       0
Bank Sta=4991.5,5015.6
Exp/Cntr=0.3,0.1

Type RM Length L Ch R = 1,145,0,0,0
BEGIN DESCRIPTION:
NORTH WILLOW CREEK 4.0
END DESCRIPTION:
XS GIS Cut Line= 3
      2762180.67     10252478.15      2762532.75     10251541.00
      2761339.66     10251168.46
#Sta/Elev= 30
  3998.9 1185.45  4029.2 1183.79  4054.1 1179.73  4114.6 1176.44  4194.6 1169.46
  4255.1 1169.79  4310.2 1164.92  4315.6 1165.84  4414.7 1161.46  4517.0 1162.16
  4566.4 1160.00  4747.9 1156.39  4796.5 1154.66  4938.1 1149.18  4958.7 1144.94
  4968.4 1144.21  4981.2 1138.08  4981.7 1137.58  5005.3 1138.08  5011.2 1139.79
  5025.4 1139.25  5038.4 1138.54  5132.8 1148.83  5336.9 1158.32  5439.0 1162.17
  5676.7 1168.95  5784.6 1175.45  5971.2 1177.59  6128.4 1182.53  6249.9 1188.27
#Mann=12,-1,0
  3998.9    0.12       0  4414.7    0.05       0  4566.4    0.12       0
  4747.9    0.05       0  4796.5    0.12       0  4958.7    0.05       0
  4981.2    0.03       0  5005.3    0.05       0  5025.4    0.12       0
  5132.8    0.05       0  5336.9    0.12       0  5439.0    0.05       0
Bank Sta=4981.2,5005.3
Exp/Cntr=0.3,0.1

Chan Stop Cuts=-1