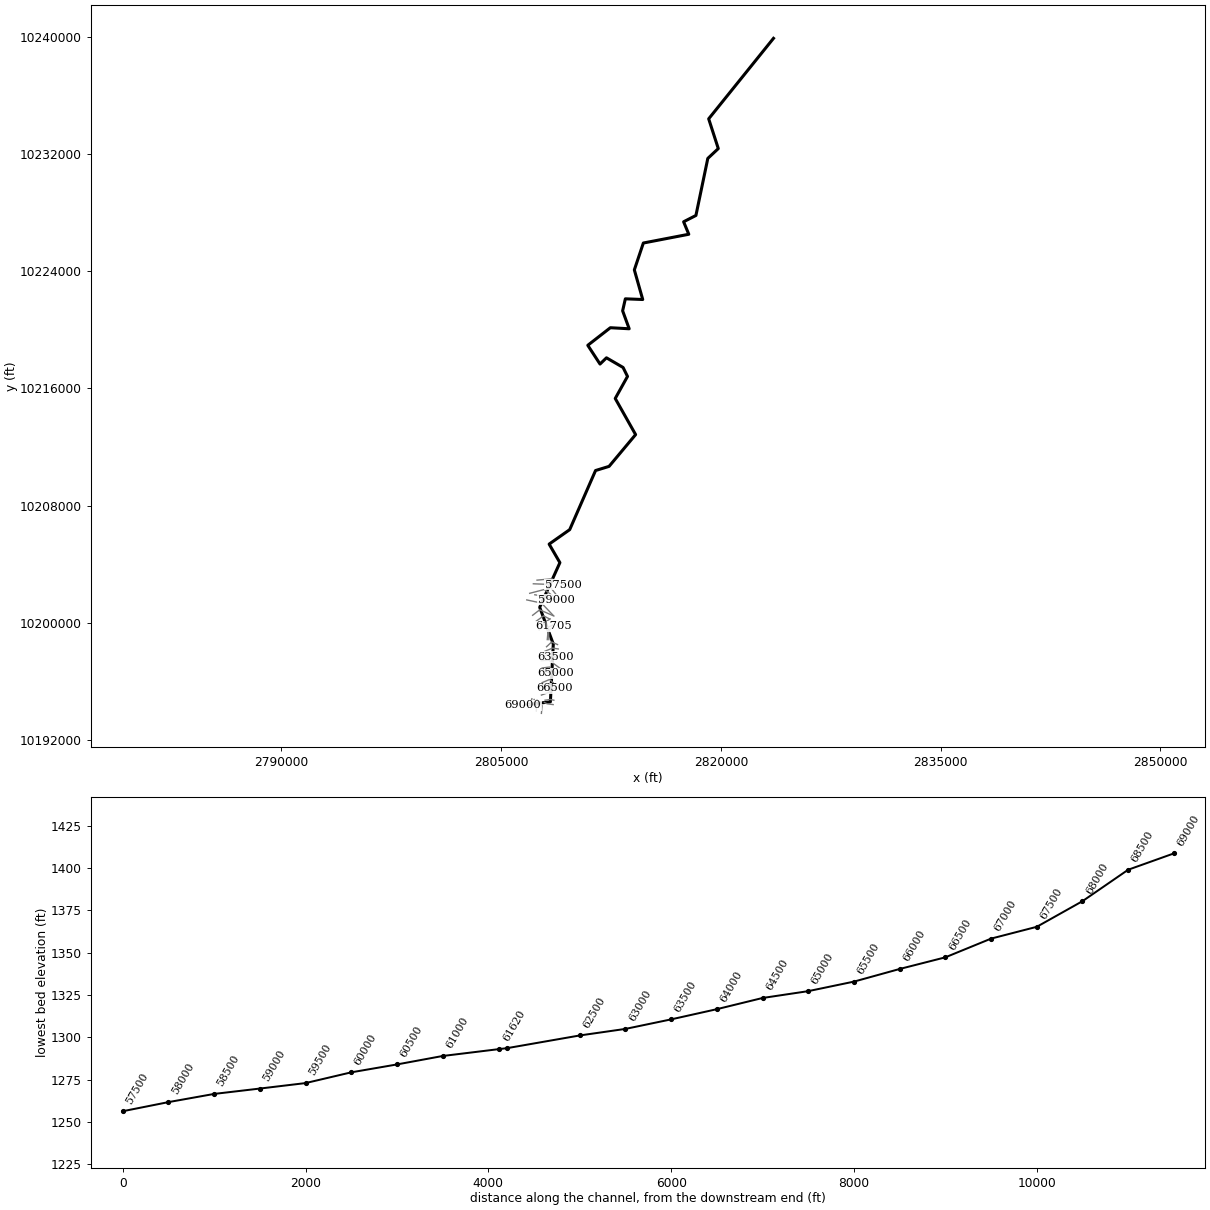
--- OATMAN CREEK.prj (project) ---

Proj Title=OATMAN CREEK Base Level Engineering
Current Plan=p01
Default Exp/Contr=0.3,0.1
English Units
Geom File=g01
Flow File=f01
Plan File=p01
Y Axis Title=Elevation
X Axis Title(PF)=Main Channel Distance
X Axis Title(XS)=Station
BEGIN DESCRIPTION:
OATMAN CREEK
END DESCRIPTION:
DSS Export Rating Curves= 0
DSS Export Rating Curve Sorted= 0
DSS Export Volume Flow Curves= 0
DXF OffsetX= 0
DXF OffsetY= 0
DXF ScaleX= 1
DXF ScaleY= 10

--- OATMAN CREEK.p01 (plan) ---

Plan Title=Multiple Run
Short Identifier=Multiple
Geom File=g01
Flow File=f01
Subcritical Flow
K Sum by GR= 0
Std Step Tol= 0.01
Critical Tol= 0.01
Num of Std Step Trials= 20
Max Error Tol= 0.3
Flow Tol Ratio= 0.001
Split Flow NTrial= 30
Split Flow Tol= 0.02
Split Flow Ratio= 0.02
Log Output Level= 0
Friction Slope Method= 1
Unsteady Friction Slope Method= 2
Unsteady Bridges Friction Slope Method= 1
Parabolic Critical Depth
Global Vel Dist=  1 , 1 , 1
Global Log Level= 0
CheckData=True
Encroach Param= -1, 0, 0, 0
BEGIN DESCRIPTION:
Multiple Run
END DESCRIPTION:

--- OATMAN CREEK.f01 (steady flow) ---

Flow Title=Multiple
Program Version=4.10
Number of Profiles= 7
Profile Names=10-year,25-year,50-year,1pct_min,100-year,1pct_plu,500-year
River Rch & RM=OATMAN CREEK,Reach-1         ,69000
     466     760    1414     902    1970    4303    2835
River Rch & RM=OATMAN CREEK,Reach-1         ,59000
     579     959    1735    1394    2428    4229    3484
River Rch & RM=OATMAN CREEK,Reach-1         ,56000
     662    1108    1991    1490    2796    5249    4004
River Rch & RM=OATMAN CREEK,Reach-1         ,54500
     849    1437    2720    1981    3856    7505    5501
River Rch & RM=OATMAN CREEK,Reach-1         ,53000
     866    1467    2769    1924    3928    8019    5602
River Rch & RM=OATMAN CREEK,Reach-1         ,52306
    1426    2489    4824    3817    6940   12619    9809
River Rch & RM=OATMAN CREEK,Reach-1         ,46651
    1558    2738    5245    4303    7563   13294   10688
River Rch & RM=OATMAN CREEK,Reach-1         ,43000
    1618    2852    5427    4269    7830   14361   11055
River Rch & RM=OATMAN CREEK,Reach-1         ,42000
    1778    3161    5832    4845    8418   14628   11860
River Rch & RM=OATMAN CREEK,Reach-1         ,38500
    1832    3266    5973    4324    8626   17207   12152
River Rch & RM=OATMAN CREEK,Reach-1         ,37000
    1964    3520    6328    4860    9144   17205   12857
River Rch & RM=OATMAN CREEK,Reach-1         ,34000
    2931    5418    9748    7745   14215   26089   19771
River Rch & RM=OATMAN CREEK,Reach-1         ,25449
    3249    6060   10582    8362   15436   28492   21389
River Rch & RM=OATMAN CREEK,Reach-1         ,19075
    3431    6431   11057   10176   16130   25567   22306
River Rch & RM=OATMAN CREEK,Reach-1         ,15189
    5542   10541   17968   13888   26117   49115   35310
River Rch & RM=OATMAN CREEK,Reach-1         ,14191
    5778   10998   18674   13859   27132   53117   36625
River Rch & RM=OATMAN CREEK,Reach-1         ,11778
    6064   11564   19419   20304   28211   39198   38015
River Rch & RM=OATMAN CREEK,Reach-1         ,6000
    6371   12165   20410   17816   29668   49404   39966
River Rch & RM=OATMAN CREEK,Reach-1         ,1963
    6399   12217   20494   25549   29786   34727   40118
Boundary for River Rch & Prof#=OATMAN CREEK,Reach-1         , 1
Up Type= 0
Dn Type= 3
Dn Slope=0.001
Boundary for River Rch & Prof#=OATMAN CREEK,Reach-1         , 2
Up Type= 0
Dn Type= 3
Dn Slope=0.001
Boundary for River Rch & Prof#=OATMAN CREEK,Reach-1         , 3
Up Type= 0
Dn Type= 3
Dn Slope=0.001
Boundary for River Rch & Prof#=OATMAN CREEK,Reach-1         , 4
Up Type= 0
Dn Type= 3
Dn Slope=0.001
Boundary for River Rch & Prof#=OATMAN CREEK,Reach-1         , 5
Up Type= 0
Dn Type= 3
Dn Slope=0.001
Boundary for River Rch & Prof#=OATMAN CREEK,Reach-1         , 6
Up Type= 0
Dn Type= 3
Dn Slope=0.001
Boundary for River Rch & Prof#=OATMAN CREEK,Reach-1         , 7
Up Type= 0
Dn Type= 3
Dn Slope=0.001
DSS Import GetInterval= 0
DSS Import GetPeak= 0
DSS Import FillOption= 0

--- OATMAN CREEK.g01 (geometry) ---

Geom Title=Existing Conditions
Program Version=4.10

River Reach=OATMAN CREEK    ,Reach-1
Reach XY= 30
        2806926.       10194427.        2808368.       10194590.
      2808567.25       10198537.      2807638.75       10201049.
      2809017.75       10204098.       2808282.5       10205363.
       2809686.5       10206352.       2811450.5       10210389.
      2812373.75       10210673.        2814185.       10212843.
        2812794.       10215310.      2813631.75       10216816.
      2813329.75       10217428.      2812195.75       10218088.
        2811756.       10217661.       2810920.5       10218942.
        2812462.       10220143.      2813746.25       10220071.
      2813298.75       10221298.      2813484.75       10222117.
      2814670.75       10222070.      2814097.75       10224093.
      2814713.25       10225928.       2817814.5       10226526.
      2817460.25       10227379.      2818300.75       10227810.
        2819112.       10231707.      2819827.25       10232378.
       2819171.5       10234410.      2823594.56     10239907.43

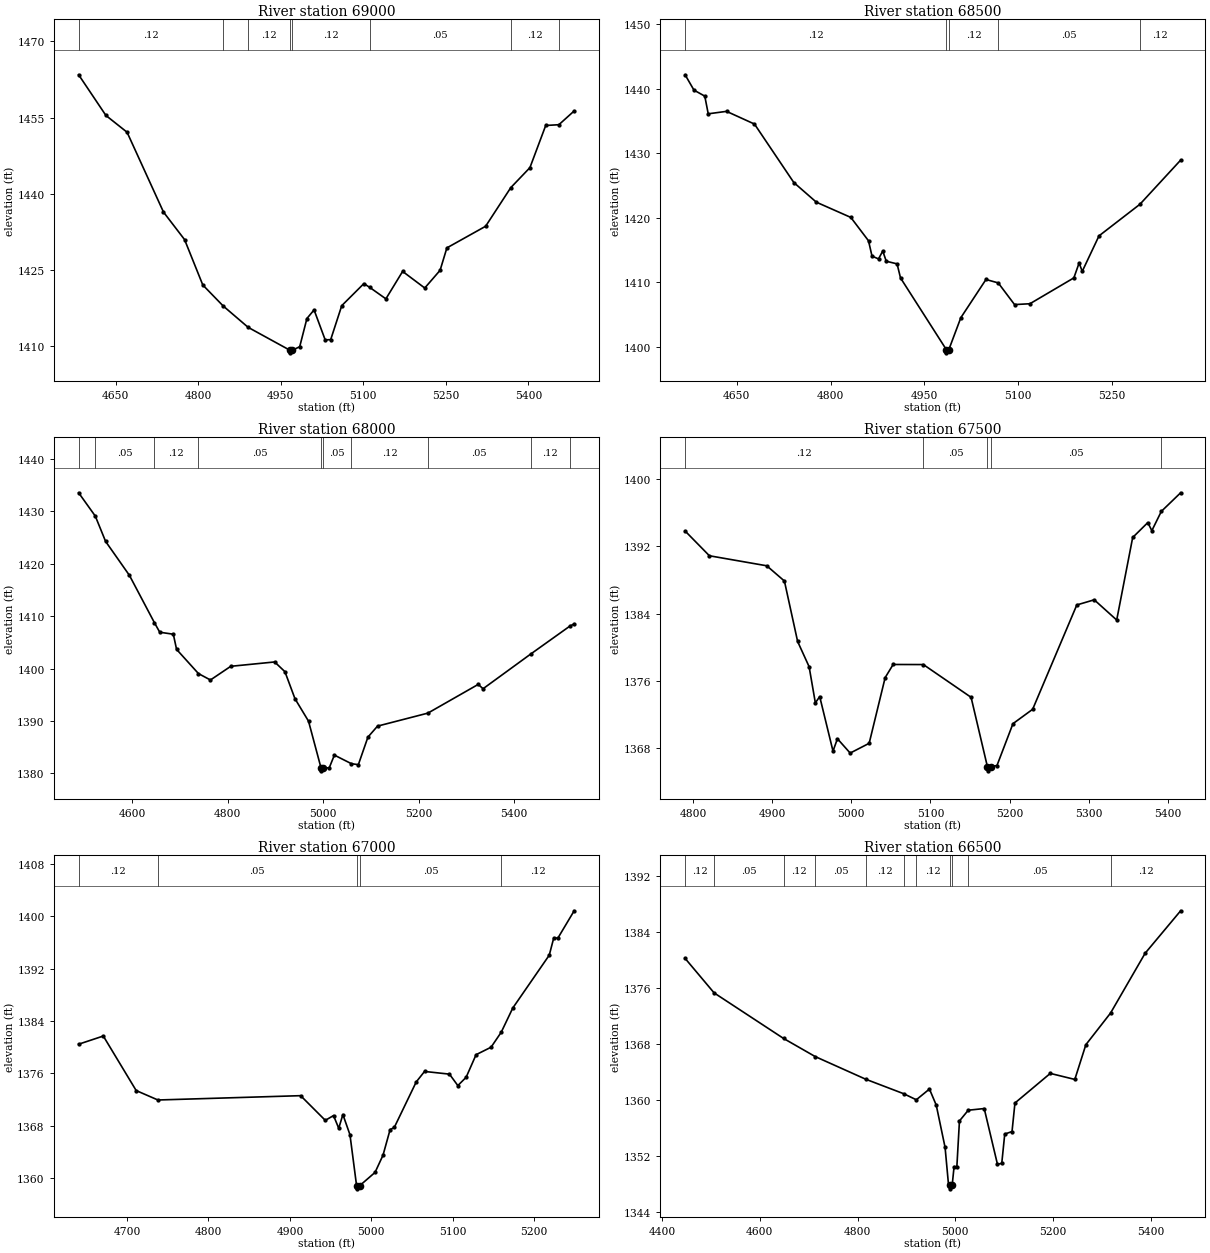
Type RM Length L Ch R = 1 ,69000   ,500,500,500
BEGIN DESCRIPTION:
OATMAN CREEK 137.0
END DESCRIPTION:
XS GIS Cut Line= 3
      2807105.67     10194803.07      2806986.17     10194403.25
      2806505.68     10194353.11
#Sta/Elev= 30
  4582.7 1463.43  4632.3 1455.42  4670.7 1452.12  4736.9  1436.4  4775.2 1430.98
  4808.3 1422.05  4845.3 1417.92  4890.7 1413.71  4966.8 1409.19  4967.1 1408.69
  4970.8 1409.19  4984.4  1409.9  4997.5 1415.45  5010.5 1417.14  5030.7 1411.24
  5040.7 1411.29  5060.8 1417.98    5101 1422.32  5111.8 1421.56    5141 1419.32
  5171.4 1424.72  5211.6 1421.45  5239.5 1424.94  5251.8 1429.35  5322.2 1433.61
  5367.9 1441.21  5402.7 1445.15  5431.4 1453.45  5455.3  1453.6  5483.1 1456.31
#Mann= 8 ,-1 , 0
  4582.7     .12       0  4845.3     .05       0  4890.7     .12       0
  4966.8     .07       0  4970.8     .12       0  5111.8     .05       0
  5367.9     .12       0  5455.3     .05       0
Bank Sta=4966.8,4970.8
XS Rating Curve= 0 ,0
Exp/Cntr=0.3,0.1

Type RM Length L Ch R = 1 ,68500   ,500,500,500
BEGIN DESCRIPTION:
OATMAN CREEK 136.0
END DESCRIPTION:
XS GIS Cut Line= 3
      2807255.67     10194753.15      2807439.63      10194361.5
      2807405.68      10194003.1
#Sta/Elev= 30
  4567.3 1442.15  4581.5 1439.77  4598.8 1438.84  4604.3  1436.1  4633.6 1436.48
  4678.3 1434.51  4741.2 1425.45  4777.3  1422.4  4832.4 1420.04  4860.7 1416.42
  4866.3 1414.04  4876.7 1413.61  4883.5 1414.83  4889.1 1413.25  4906.4 1412.84
  4911.9 1410.66  4985.2 1399.55  4985.4 1399.05  4989.2 1399.55  5008.4  1404.5
  5048.6 1410.42  5068.2 1409.89  5094.3 1406.53  5118.9 1406.66  5189.2 1410.67
  5197.6 1412.98  5202.6 1411.68  5229.4 1417.18  5294.9 1422.08    5360 1428.92
#Mann= 5 ,-1 , 0
  4567.3     .12       0  4985.2     .07       0  4989.2     .12       0
  5068.2     .05       0  5294.9     .12       0
Bank Sta=4985.2,4989.2
XS Rating Curve= 0 ,0
Exp/Cntr=0.3,0.1

Type RM Length L Ch R = 1 ,68000   ,500,500,500
BEGIN DESCRIPTION:
OATMAN CREEK 135.0
END DESCRIPTION:
XS GIS Cut Line= 3
       2807455.7     10194703.09      2807802.22     10194326.58
      2807755.69     10193803.15
#Sta/Elev= 30
  4488.3 1433.52  4523.2 1429.07  4544.7 1424.25  4594.6 1417.77  4646.8 1408.76
  4658.1 1406.92  4686.5 1406.54  4693.3 1403.65  4739.1 1399.03  4764.2 1397.81
  4806.7 1400.42  4898.6 1401.25  4920.1 1399.39  4941.1 1394.24  4969.5 1389.95
  4995.8 1380.98  4996.1 1380.48  4999.8 1380.98  5012.9 1381.07  5023.6 1383.48
  5059.3 1381.84  5073.8 1381.66  5093.8 1386.91  5113.9 1389.01  5219.3 1391.49
  5324.7 1396.97  5334.8 1396.14  5434.1 1402.73  5516.4 1408.08  5525.5 1408.51
#Mann= 10 ,-1 , 0
  4488.3     .12       0  4523.2     .05       0  4646.8     .12       0
  4739.1     .05       0  4995.8     .05       0  4999.8     .05       0
  5059.3     .12       0  5219.3     .05       0  5434.1     .12       0
  5516.4     .05       0
Bank Sta=4995.8,4999.8
XS Rating Curve= 0 ,0
Exp/Cntr=0.3,0.1

Type RM Length L Ch R = 1 ,67500   ,500,500,500
BEGIN DESCRIPTION:
OATMAN CREEK 134.0
END DESCRIPTION:
XS GIS Cut Line= 3
      2807955.69     10194553.11      2808143.25     10194458.67
      2808555.73     10194403.11
#Sta/Elev= 30
    4790 1393.82  4820.7 1390.88  4893.2 1389.69  4915.5 1387.88  4932.2  1380.7
  4946.7 1377.71  4954.6 1373.41  4960.1 1374.16  4976.9 1367.68  4982.5 1369.15
  4998.6 1367.45  5022.6 1368.61  5042.8 1376.41  5052.9 1377.97  5091.1 1377.96
  5151.4 1374.07    5172 1365.84  5172.2 1365.34    5176 1365.84  5184.1 1365.97
  5204.3 1370.94  5229.2 1372.65    5285 1385.04    5307 1385.65  5335.4 1383.25
  5355.6 1393.05  5374.7 1394.82  5379.8 1393.86  5391.8 1396.15  5416.2 1398.36
#Mann= 5 ,-1 , 0
    4790     .12       0  5091.1     .05       0    5172     .07       0
    5176     .05       0  5391.8     .12       0
Bank Sta=5172,5176
XS Rating Curve= 0 ,0
Exp/Cntr=0.3,0.1

Type RM Length L Ch R = 1 ,67000   ,500,500,500
BEGIN DESCRIPTION:
OATMAN CREEK 133.0
END DESCRIPTION:
XS GIS Cut Line= 3
      2808005.67     10194703.11      2808361.62     10194753.52
      2808605.67     10194703.11
#Sta/Elev= 30
  4640.5 1380.46  4670.8 1381.71  4711.2 1373.38  4737.9 1371.94  4913.2  1372.6
  4943.5 1368.83  4953.6 1369.56    4960 1367.62  4965.1 1369.72  4973.8 1366.63
  4981.9 1358.87  4982.2 1358.37  4985.9 1358.87  5004.6 1360.88  5014.4 1363.51
  5023.1 1367.42  5028.2 1367.74  5055.2  1374.7  5065.4  1376.3    5096 1375.89
  5106.3 1374.14  5116.5 1375.41  5128.7 1378.86  5147.1    1380  5159.6 1382.29
  5173.8 1385.99  5218.6 1394.06  5224.1 1396.69  5229.2 1396.67  5249.2 1400.84
#Mann= 5 ,-1 , 0
  4640.5     .12       0  4737.9     .05       0  4981.9     .03       0
  4985.9     .05       0  5159.6     .12       0
Bank Sta=4981.9,4985.9
XS Rating Curve= 0 ,0
Exp/Cntr=0.3,0.1

Type RM Length L Ch R = 1 ,66500   ,500,500,500
BEGIN DESCRIPTION:
OATMAN CREEK 132.0
END DESCRIPTION:
XS GIS Cut Line= 3
      2807755.68     10195053.11      2808275.26     10195242.15
      2808655.66      10195503.1
#Sta/Elev= 30
  4447.1 1380.18  4506.5 1375.26  4648.5 1368.77  4713.4 1366.18  4816.8 1362.95
  4894.6 1360.88  4920.3 1360.02  4947.2 1361.55  4961.1 1359.26  4979.2 1353.23
  4986.3 1347.85  4989.7 1347.82  4989.9 1347.32  4993.7 1347.82  4997.6 1350.48
  5003.3 1350.48  5008.6    1357  5026.6 1358.53  5059.3 1358.77  5086.4 1350.82
  5095.2 1350.96  5101.3 1355.13  5116.2 1355.49  5122.2 1359.56  5194.5 1363.78
  5244.7 1362.92  5267.3 1367.87  5317.9 1372.39  5388.6 1380.91  5461.3 1386.97
#Mann= 11 ,-1 , 0
  4447.1     .12       0  4506.5     .05       0  4648.5     .12       0
  4713.4     .05       0  4816.8     .12       0  4894.6     .05       0
  4920.3     .12       0  4989.7     .07       0  4993.7     .12       0
  5026.6     .05       0  5317.9     .12       0
Bank Sta=4989.7,4993.7
XS Rating Curve= 0 ,0
Exp/Cntr=0.3,0.1

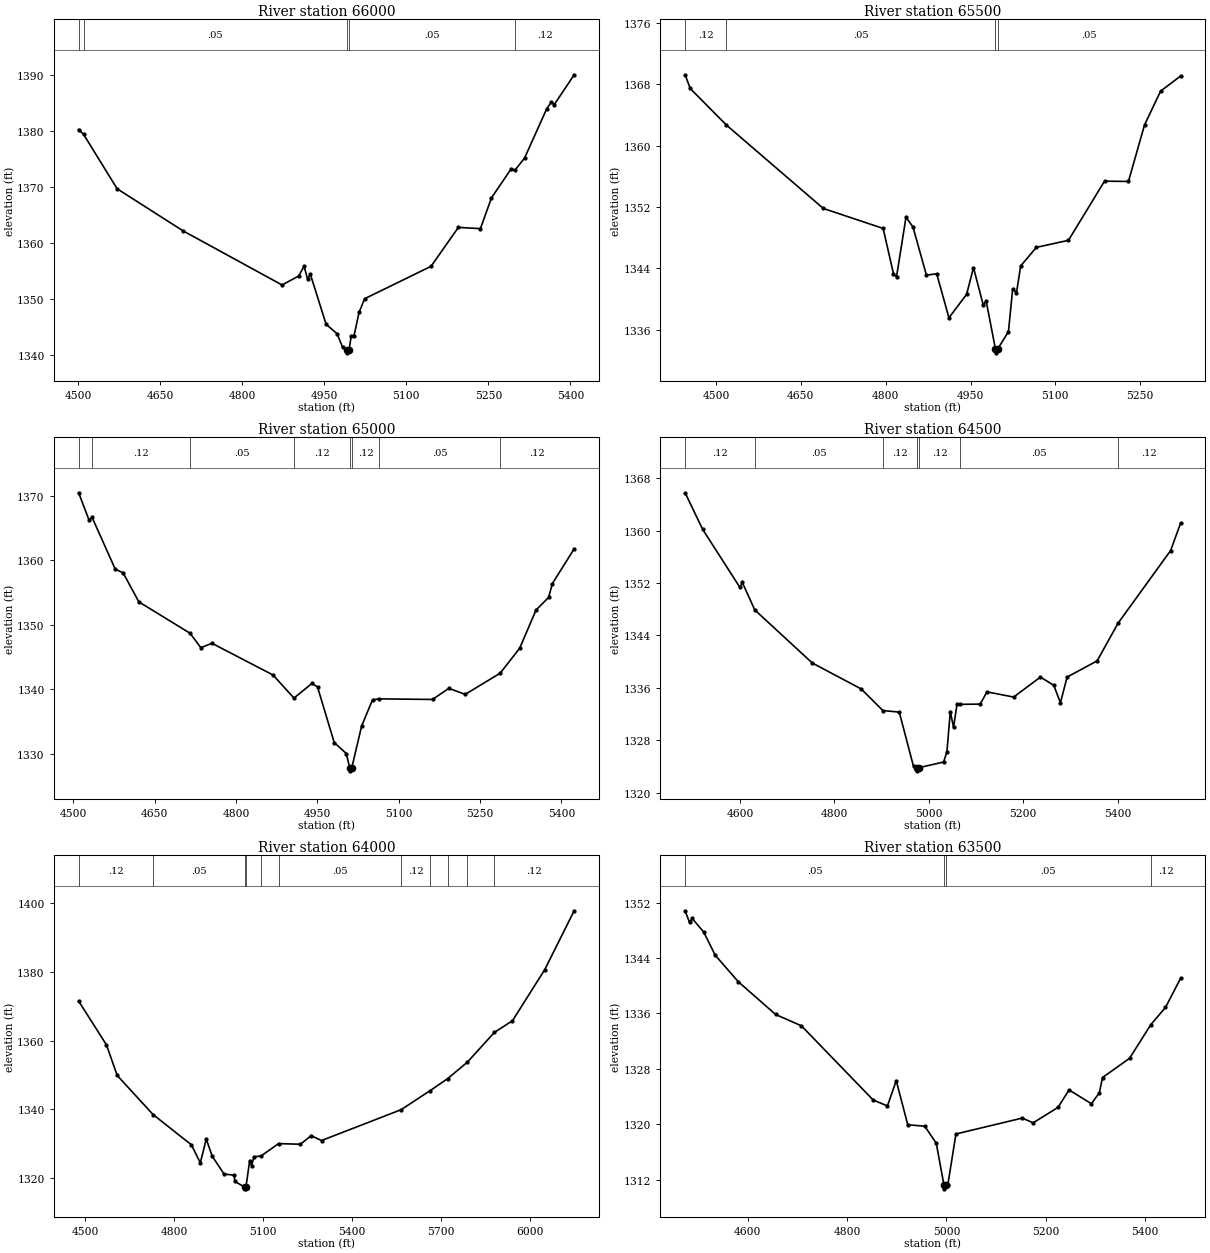
Type RM Length L Ch R = 1 ,66000   ,500,500,500
BEGIN DESCRIPTION:
OATMAN CREEK 131.0
END DESCRIPTION:
XS GIS Cut Line= 3
      2807755.69     10195653.11      2808252.22      10195706.6
      2808655.69     10195653.11
#Sta/Elev= 30
  4500.6 1380.26  4509.7  1379.4    4571  1369.7  4691.7 1362.19  4872.7 1352.54
  4902.9 1354.13    4913 1355.87  4919.4 1353.57  4924.4 1354.47  4953.2 1345.54
  4973.3 1343.85  4983.4 1341.44  4991.4 1340.94  4991.7 1340.44  4995.4 1340.94
  4999.2 1343.49  5004.3 1343.49  5013.6 1347.67  5023.7 1350.09  5145.2 1355.87
  5195.2 1362.81  5235.5 1362.59  5255.7 1368.07  5291.9 1373.28  5298.7 1373.02
  5316.2 1375.17  5356.6 1383.93  5365.3 1385.18  5370.3 1384.67    5407 1390.03
#Mann= 5 ,-1 , 0
  4500.6     .12       0  4509.7     .05       0  4991.4     .05       0
  4995.4     .05       0  5298.7     .12       0
Bank Sta=4991.4,4995.4
XS Rating Curve= 0 ,0
Exp/Cntr=0.3,0.1

Type RM Length L Ch R = 1 ,65500   ,500,500,500
BEGIN DESCRIPTION:
OATMAN CREEK 130.0
END DESCRIPTION:
XS GIS Cut Line= 3
      2807805.69     10195903.11      2808316.85     10196118.52
      2808555.67     10195903.13
#Sta/Elev= 30
  4445.3 1369.26  4454.4 1367.47  4518.5 1362.69  4689.7 1351.82  4795.5 1349.21
  4813.8 1343.31  4819.2 1342.91    4836  1350.7  4848.3 1349.39  4872.1 1343.11
  4890.2  1343.3  4911.9 1337.55  4943.2 1340.63  4955.3  1344.1  4972.4 1339.25
  4977.8  1339.7  4994.1 1333.48  4994.4 1332.98  4998.1 1333.48  5017.1 1335.74
  5024.6 1341.34  5031.3  1340.8  5038.7 1344.31  5066.4 1346.74  5123.2 1347.66
    5187 1355.38  5229.3 1355.34  5257.7 1362.71  5286.1 1367.12  5321.6  1369.1
#Mann= 4 ,-1 , 0
  4445.3     .12       0  4518.5     .05       0  4994.1     .05       0
  4998.1     .05       0
Bank Sta=4994.1,4998.1
XS Rating Curve= 0 ,0
Exp/Cntr=0.3,0.1

Type RM Length L Ch R = 1 ,65000   ,500,500,500
BEGIN DESCRIPTION:
OATMAN CREEK 129.0
END DESCRIPTION:
XS GIS Cut Line= 3
      2807805.68     10196703.11      2808284.37     10196596.11
      2808705.68     10196553.11
#Sta/Elev= 30
  4509.5 1370.47  4528.6 1366.26  4534.3 1366.66  4577.2 1358.59  4591.5 1358.07
  4620.6 1353.55    4715 1348.69  4734.9 1346.45  4755.4 1347.13  4868.1 1342.21
  4906.7 1338.63  4939.9 1340.91  4950.1 1340.36  4980.9 1331.74  5003.2 1330.03
  5009.4 1327.85  5009.6 1327.35  5013.4 1327.85  5031.5 1334.31  5051.6 1338.37
    5064 1338.51  5162.2 1338.42  5192.3 1340.14  5222.5 1339.21    5287 1342.49
    5323 1346.36  5353.1 1352.28  5376.3 1354.24  5383.3 1356.39  5423.5 1361.78
#Mann= 8 ,-1 , 0
  4509.5     .05       0  4534.3     .12       0    4715     .05       0
  4906.7     .12       0  5009.4     .07       0  5013.4     .12       0
    5064     .05       0    5287     .12       0
Bank Sta=5009.4,5013.4
XS Rating Curve= 0 ,0
Exp/Cntr=0.3,0.1

Type RM Length L Ch R = 1 ,64500   ,500,500,500
BEGIN DESCRIPTION:
OATMAN CREEK 128.0
END DESCRIPTION:
XS GIS Cut Line= 3
      2807805.69     10196903.11       2808317.7     10196969.58
      2808705.69     10196603.11
#Sta/Elev= 30
  4483.7 1365.78  4520.8 1360.21  4599.9 1351.32    4605 1352.08  4631.4 1347.88
  4753.2 1339.78  4856.8 1335.82  4902.7 1332.52  4937.5 1332.28  4967.7 1323.98
  4975.8 1323.81  4976.1 1323.31  4979.8 1323.81  5031.4 1324.65  5038.5 1326.23
  5045.6 1332.36  5052.5 1329.96  5059.8 1333.45  5066.8 1333.47  5109.1  1333.5
  5123.3 1335.37  5179.9 1334.58  5236.6 1337.63  5264.9 1336.37    5279 1333.71
  5293.2 1337.64  5356.7  1340.1  5400.9 1345.84  5512.5 1356.96  5533.7 1361.15
#Mann= 7 ,-1 , 0
  4483.7     .12       0  4631.4     .05       0  4902.7     .12       0
  4975.8     .07       0  4979.8     .12       0  5066.8     .05       0
  5400.9     .12       0
Bank Sta=4975.8,4979.8
XS Rating Curve= 0 ,0
Exp/Cntr=0.3,0.1

Type RM Length L Ch R = 1 ,64000   ,500,500,500
BEGIN DESCRIPTION:
OATMAN CREEK 127.0
END DESCRIPTION:
XS GIS Cut Line= 3
      2807755.67     10197403.11      2808276.71      10197431.3
      2809205.69      10196753.1
#Sta/Elev= 30
  4478.2 1371.51  4572.1 1358.73  4608.4 1349.79  4729.2  1338.4  4858.8 1329.54
  4888.8 1324.29  4908.8 1331.24  4928.9 1326.23  4968.9 1321.01  5002.5 1320.69
  5005.2 1318.87  5038.7  1317.2  5038.9  1316.7  5042.7  1317.2  5055.4 1324.96
  5061.6 1323.44    5070 1326.04  5094.1 1326.31  5152.6  1329.9  5226.8 1329.72
  5262.4 1332.23  5297.9  1330.8  5566.4 1339.81  5663.4 1345.32  5723.8  1348.9
  5789.6 1353.66  5881.2 1362.38    5942 1365.77  6050.9 1380.69  6150.2 1397.87
#Mann= 11 ,-1 , 0
  4478.2     .12       0  4729.2     .05       0  5038.7     .05       0
  5042.7     .05       0  5094.1     .12       0  5152.6     .05       0
  5566.4     .12       0  5663.4     .05       0  5723.8     .12       0
  5789.6     .05       0  5881.2     .12       0
Bank Sta=5038.7,5042.7
XS Rating Curve= 0 ,0
Exp/Cntr=0.3,0.1

Type RM Length L Ch R = 1 ,63500   ,500,500,500
BEGIN DESCRIPTION:
OATMAN CREEK 126.0
END DESCRIPTION:
XS GIS Cut Line= 3
      2807805.69     10197653.11        2808286.     10197868.03
      2808705.67     10197653.12
#Sta/Elev= 30
  4473.8 1350.82  4482.7 1349.14  4488.1 1349.71  4511.3 1347.75  4534.5  1344.4
  4580.9 1340.58    4656 1335.85  4707.9 1334.22  4852.5  1323.5  4881.2 1322.65
  4898.9  1326.3  4922.1 1319.93  4956.3 1319.72  4979.5 1317.26  4995.1 1311.18
  4995.3 1310.68  4999.1 1311.18  5002.6 1311.18  5019.1  1318.6  5152.4 1320.89
  5174.6 1320.21  5224.6 1322.44  5246.8 1324.96  5291.8 1322.97  5307.8 1324.54
  5314.2 1326.75  5368.8 1329.53  5411.3 1334.37    5441 1336.87  5471.5 1341.08
#Mann= 4 ,-1 , 0
  4473.8     .05       0  4995.1     .05       0  4999.1     .05       0
  5411.3     .12       0
Bank Sta=4995.1,4999.1
XS Rating Curve= 0 ,0
Exp/Cntr=0.3,0.1

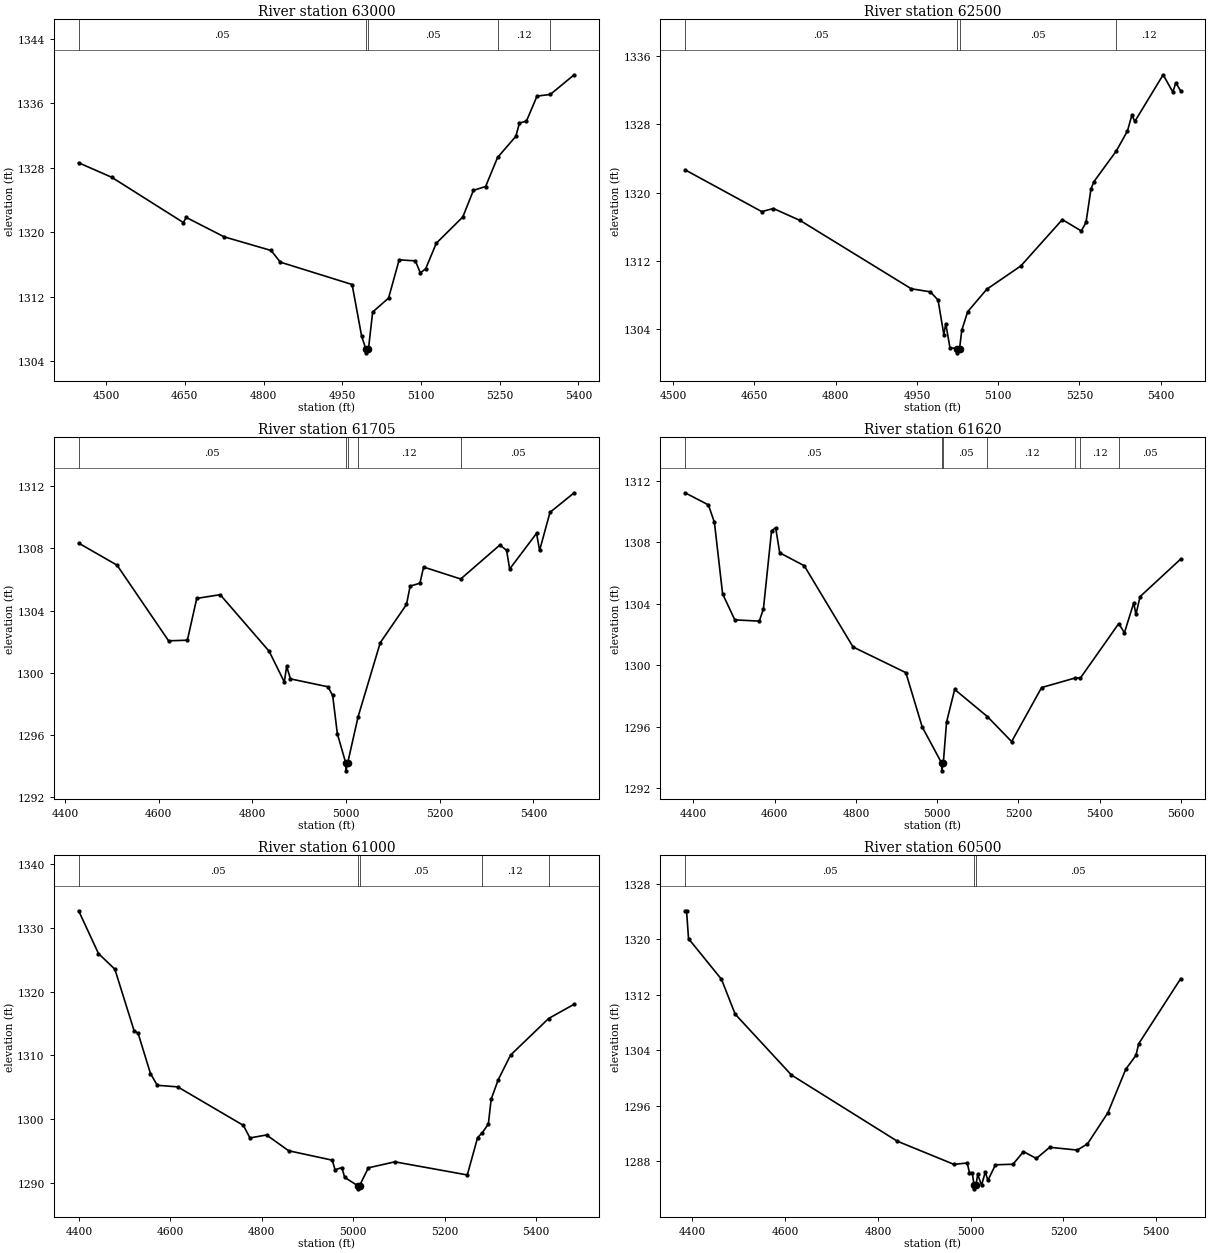
Type RM Length L Ch R = 1 ,63000   ,500,500,500
BEGIN DESCRIPTION:
OATMAN CREEK 125.0
END DESCRIPTION:
XS GIS Cut Line= 3
      2808005.72     10198053.13      2808517.81     10198260.53
      2808905.68     10198203.11
#Sta/Elev= 30
  4447.5 1328.61  4510.4 1326.82  4647.2  1321.2  4652.5 1321.84  4724.9 1319.43
  4814.3 1317.74  4832.1 1316.29  4968.8 1313.52  4986.9 1307.13  4994.8 1305.55
    4995 1305.05  4998.8 1305.55    5000 1305.55    5008 1310.11  5038.3 1311.84
  5058.5 1316.58  5089.4 1316.45  5098.9 1314.96    5109 1315.47  5129.3 1318.64
  5179.8 1321.89    5200 1325.19  5223.3 1325.67  5246.1 1329.27  5280.9 1331.89
  5287.8 1333.54  5301.1 1333.77  5321.3 1336.88  5346.6 1337.08  5392.1 1339.52
#Mann= 5 ,-1 , 0
  4447.5     .05       0  4994.8     .03       0  4998.8     .05       0
  5246.1     .12       0  5346.6     .05       0
Bank Sta=4994.8,4998.8
XS Rating Curve= 0 ,0
Exp/Cntr=0.3,0.1

Type RM Length L Ch R = 1 ,62500   ,795,795,795
BEGIN DESCRIPTION:
OATMAN CREEK 124.0
END DESCRIPTION:
XS GIS Cut Line= 3
      2808105.68      10198353.1      2808455.64     10198678.55
      2808855.66     10198503.12
#Sta/Elev= 30
  4522.1 1322.66  4663.6 1317.76  4685.1 1318.12  4734.4 1316.72  4939.6  1308.7
  4974.8 1308.34    4989 1307.38  4999.7 1303.33  5003.3  1304.6    5011 1301.77
  5024.7 1301.68  5024.9 1301.18  5028.7 1301.68  5032.8 1303.82  5043.7 1306.01
  5078.9 1308.64    5142 1311.39  5218.4 1316.82  5253.4 1315.49  5262.1 1316.48
  5271.3 1320.42  5276.7 1321.27  5318.3  1324.9  5338.6 1327.22  5346.8 1329.08
  5352.3 1328.35  5404.5 1333.82  5422.4 1331.79  5427.9 1332.88  5436.8 1331.94
#Mann= 4 ,-1 , 0
  4522.1     .05       0  5024.7     .05       0  5028.7     .05       0
  5318.3     .12       0
Bank Sta=5024.7,5028.7
XS Rating Curve= 0 ,0
Exp/Cntr=0.3,0.1

Type RM Length L Ch R = 1 ,61705   ,85,85,85
BEGIN DESCRIPTION:
Mapping XS 777e2cae
END DESCRIPTION:
XS GIS Cut Line= 4
       2808263.8     10198841.18      2808249.94     10199247.57
      2808254.56     10199459.99       2808593.2     10199738.73
#Sta/Elev= 30
  4429.2 1308.34  4511.2 1306.92  4621.2 1302.05  4661.3 1302.09  4681.3 1304.78
  4731.3 1305.02  4835.8 1301.38  4868.2  1299.4  4873.2  1300.4  4881.4  1299.6
  4961.4 1299.09  4971.4 1298.53  4981.4 1296.07  4999.4 1294.18  4999.7 1293.68
  5003.4 1294.18  5025.7 1297.16    5073 1301.93    5129 1304.39  5136.8 1305.57
  5157.7 1305.76  5165.5  1306.8  5244.7 1306.03  5328.4 1308.22  5342.7 1307.87
  5349.2 1306.67  5406.6 1308.97  5413.1 1307.87  5435.3 1310.32  5486.9 1311.58
#Mann= 5 ,-1 , 0
  4429.2     .05       0  4999.4     .05       0  5003.4     .05       0
  5025.7     .12       0  5244.7     .05       0
Bank Sta=4999.4,5003.4
XS Rating Curve= 0 ,0
Exp/Cntr=0.3,0.1

Type RM Length L Ch R = 1 ,61620   ,620,620,620
BEGIN DESCRIPTION:
Mapping XS 6cc848ac
END DESCRIPTION:
XS GIS Cut Line= 6
      2808155.28      10198841.2       2808187.6     10199185.23
       2808187.6     10199397.65      2808180.68     10199559.27
       2808187.6     10199674.71      2808536.27     10199836.35
#Sta/Elev= 30
  4379.4 1311.21  4436.9 1310.42  4451.6 1309.28  4471.7 1304.64  4501.8 1302.95
  4562.1 1302.87  4572.2 1303.67  4592.2 1308.74  4602.3 1308.94  4612.3 1307.31
  4672.6 1306.47  4792.8 1301.19  4922.8 1299.52  4962.9    1296  5010.9 1293.64
  5011.1 1293.14  5014.9 1293.64  5022.9  1296.3  5042.9 1298.43  5123.7 1296.66
  5183.1 1295.04  5256.8 1298.55  5340.1 1299.18  5352.6 1299.18  5446.8 1302.71
  5460.7 1302.11  5483.6 1304.05  5489.1 1303.31  5499.2 1304.46  5599.1  1306.9
#Mann= 7 ,-1 , 0
  4379.4     .05       0  5010.9     .05       0  5014.9     .05       0
  5123.7     .12       0  5340.1     .05       0  5352.6     .12       0
  5446.8     .05       0
Bank Sta=5010.9,5014.9
XS Rating Curve= 0 ,0
Exp/Cntr=0.3,0.1

Type RM Length L Ch R = 1 ,61000   ,500,500,500
BEGIN DESCRIPTION:
OATMAN CREEK 121.0
END DESCRIPTION:
XS GIS Cut Line= 3
       2807605.7     10199503.13      2807943.69     10199999.96
      2808355.72     10200253.14
#Sta/Elev= 30
  4399.1 1332.71  4442.5    1326  4478.4 1323.53  4520.4  1313.9  4529.2 1313.48
  4556.3 1307.16  4571.2 1305.31    4616 1305.06  4759.7 1299.01    4774 1297.04
  4810.3 1297.51  4858.7 1295.03  4954.2 1293.55  4960.3 1292.04  4975.2 1292.39
  4981.3 1290.84  5009.9 1289.55  5010.1 1289.05  5013.9 1289.55  5033.2 1292.35
  5091.2 1293.29  5249.7 1291.23  5272.3 1297.11  5282.5 1297.85  5295.8 1299.24
  5301.9 1303.11  5317.3 1306.17  5344.4 1310.05  5427.6 1315.79  5483.6 1318.04
#Mann= 5 ,-1 , 0
  4399.1     .05       0  5009.9     .03       0  5013.9     .05       0
  5282.5     .12       0  5427.6     .05       0
Bank Sta=5009.9,5013.9
XS Rating Curve= 0 ,0
Exp/Cntr=0.3,0.1

Type RM Length L Ch R = 1 ,60500   ,500,500,500
BEGIN DESCRIPTION:
OATMAN CREEK 120.0
END DESCRIPTION:
XS GIS Cut Line= 3
      2807405.67      10200103.1      2807904.88     10200463.82
      2808305.67     10200253.12
#Sta/Elev= 30
  4384.1 1324.08  4387.2 1324.08  4391.5 1320.07  4462.6 1314.22    4492 1309.21
  4613.5 1300.44  4841.7 1290.92    4964 1287.58  4992.5 1287.78  4997.4 1286.39
  5003.3 1286.39  5007.4 1284.56  5007.7 1284.06  5011.4 1284.56  5015.1 1286.13
  5023.5 1284.58  5031.5 1286.49  5037.1 1285.28  5053.5 1287.52  5091.3  1287.6
  5113.9 1289.42  5141.7 1288.43  5170.4 1290.04  5229.8 1289.64  5251.9 1290.53
    5296 1295.02  5334.4 1301.27  5356.4 1303.27  5362.4 1304.95  5452.8  1314.3
#Mann= 3 ,-1 , 0
  4384.1     .05       0  5007.4     .03       0  5011.4     .05       0
Bank Sta=5007.4,5011.4
XS Rating Curve= 0 ,0
Exp/Cntr=0.3,0.1

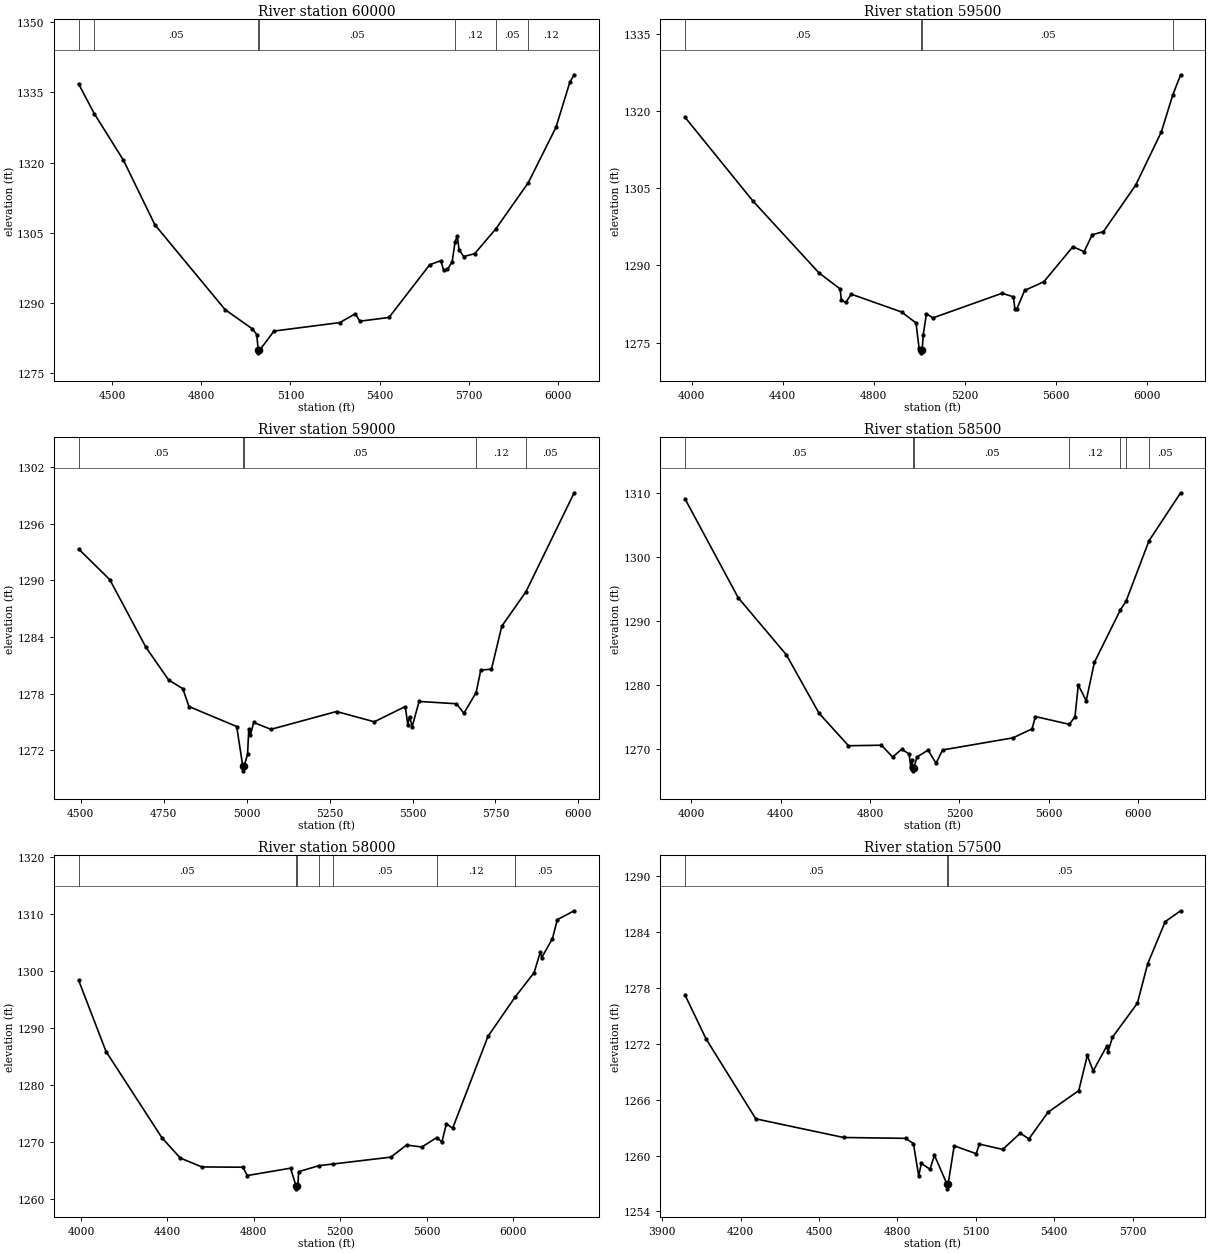
Type RM Length L Ch R = 1 ,60000   ,500,500,500
BEGIN DESCRIPTION:
OATMAN CREEK 119.0
END DESCRIPTION:
XS GIS Cut Line= 3
      2807155.67      10200503.1      2807640.59     10200876.46
      2808605.71      10200453.1
#Sta/Elev= 30
    4388  1336.8  4440.7 1330.46  4538.4 1320.56  4644.4 1306.74  4880.2 1288.64
  4972.4  1284.5  4986.9  1283.3  4991.8  1279.9    4992  1279.4  4995.8  1279.9
  5044.7 1284.05    5266 1285.86  5318.1 1287.74  5333.2 1286.16  5431.4 1286.95
  5568.2 1298.21  5606.2 1299.09  5614.9 1297.01    5628  1297.2  5643.8 1298.88
  5653.5 1303.06  5660.8 1304.35  5667.1 1301.38  5682.6 1299.96  5719.3 1300.57
    5790 1305.82  5899.9 1315.76  5992.7 1327.55  6039.5 1337.22  6053.9 1338.77
#Mann= 7 ,-1 , 0
    4388     .12       0  4440.7     .05       0  4991.8     .03       0
  4995.8     .05       0  5653.5     .12       0    5790     .05       0
  5899.9     .12       0
Bank Sta=4991.8,4995.8
XS Rating Curve= 0 ,0
Exp/Cntr=0.3,0.1

Type RM Length L Ch R = 1 ,59500   ,500,500,500
BEGIN DESCRIPTION:
OATMAN CREEK 118.0
END DESCRIPTION:
XS GIS Cut Line= 3
      2806755.71     10201553.11      2807761.45     10201334.61
       2808555.7     10200503.09
#Sta/Elev= 30
  3970.8 1318.74  4267.5 1302.59  4559.4 1288.57  4652.5 1285.45  4657.7 1283.33
  4676.9 1282.82  4701.7 1284.43  4922.5 1280.98  4986.2 1278.85  4999.6 1273.99
  5009.2 1273.55  5009.4 1273.05  5013.2 1273.55  5018.1 1276.59  5032.2 1280.65
  5060.6 1279.83  5364.7 1284.61  5414.4 1283.92  5421.3  1281.5  5428.5 1281.46
  5463.8 1285.15  5548.7 1286.86  5676.1 1293.64  5725.4 1292.68    5761 1295.95
  5810.4 1296.57  5951.9 1305.56  6065.1 1315.92  6115.1 1323.06  6149.9    1327
#Mann= 4 ,-1 , 0
  3970.8     .05       0  5009.2     .03       0  5013.2     .05       0
  6115.1     .12       0
Bank Sta=5009.2,5013.2
XS Rating Curve= 0 ,0
Exp/Cntr=0.3,0.1

Type RM Length L Ch R = 1 ,59000   ,500,500,500
BEGIN DESCRIPTION:
OATMAN CREEK 117.0
END DESCRIPTION:
XS GIS Cut Line= 3
      2807305.71     10201903.11      2807805.25     10201820.05
      2808755.68     10201553.11
#Sta/Elev= 30
  4493.6 1293.34  4587.5 1290.09  4696.3 1282.93  4765.1 1279.44  4807.8 1278.53
    4826 1276.64    4970 1274.52  4988.3 1270.32  4988.5 1269.82  4992.4 1270.32
  5002.8 1271.58  5006.4 1274.24  5011.6 1273.63  5021.2 1274.95  5073.2 1274.22
  5270.9 1276.11  5384.8 1275.02  5478.2 1276.64  5485.7 1274.72  5490.9 1275.57
    5499 1274.52  5519.8 1277.18  5632.4 1276.93  5654.8 1275.92  5691.7 1278.12
  5705.7  1280.5  5737.9  1280.6  5769.1 1285.16  5841.7  1288.8  5987.2  1299.3
#Mann= 5 ,-1 , 0
  4493.6     .05       0  4988.3     .05       0  4992.4     .05       0
  5691.7     .12       0  5841.7     .05       0
Bank Sta=4988.3,4992.4
XS Rating Curve= 0 ,0
Exp/Cntr=0.3,0.1

Type RM Length L Ch R = 1 ,58500   ,500,500,500
BEGIN DESCRIPTION:
OATMAN CREEK 116.0
END DESCRIPTION:
XS GIS Cut Line= 3
      2806955.69     10202003.11      2807949.51     10202262.06
      2808905.66     10201553.13
#Sta/Elev= 30
    3973 1308.99  4210.7 1293.61  4425.8 1284.74  4572.4 1275.62  4704.1 1270.56
  4851.4 1270.64  4901.5 1268.81    4942 1270.01  4975.4 1269.28  4982.5  1267.3
  4987.6 1268.39  4993.4 1267.15  4993.6 1266.65  4997.5 1267.15  5010.3  1268.8
  5060.4 1269.89  5095.8 1267.82  5125.1  1269.9  5440.2 1271.79  5525.7 1273.19
  5540.3 1275.11  5692.5 1273.89  5717.7 1275.11  5732.3 1280.02  5767.7 1277.57
  5804.4 1283.55  5919.7 1291.65  5946.4  1293.1  6048.7 1302.48  6190.3 1309.96
#Mann= 7 ,-1 , 0
    3973     .05       0  4993.4     .05       0  4997.5     .05       0
  5692.5     .12       0  5919.7     .05       0  5946.4     .12       0
  6048.7     .05       0
Bank Sta=4993.4,4997.5
XS Rating Curve= 0 ,0
Exp/Cntr=0.3,0.1

Type RM Length L Ch R = 1 ,58000   ,500,500,500
BEGIN DESCRIPTION:
OATMAN CREEK 115.0
END DESCRIPTION:
XS GIS Cut Line= 3
      2807205.65     10202653.11      2808215.98     10202613.78
      2809005.68     10201603.12
#Sta/Elev= 30
  3988.9 1298.36  4115.8 1285.88  4374.4 1270.77  4459.3 1267.21  4559.4 1265.65
  4749.5  1265.6  4769.5 1264.14  4969.7 1265.43  4995.3 1262.31  4995.6 1261.81
  4999.4 1262.31  5003.6 1262.31  5007.4 1264.82  5101.8 1265.88  5164.1 1266.15
  5434.3 1267.37  5506.6 1269.49  5577.2 1269.14  5646.7  1270.8  5670.3 1270.03
  5691.1  1273.2  5720.1 1272.43  5883.8 1288.55  6008.7  1295.4  6097.2 1299.71
  6126.1 1303.34  6132.5 1302.35  6182.2 1305.69  6204.8    1309  6282.6 1310.55
#Mann= 7 ,-1 , 0
  3988.9     .05       0  4995.3     .05       0  4999.4     .05       0
  5101.8     .12       0  5164.1     .05       0  5646.7     .12       0
  6008.7     .05       0
Bank Sta=4995.3,4999.4
XS Rating Curve= 0 ,0
Exp/Cntr=0.3,0.1

Type RM Length L Ch R = 1 ,57500   ,492,492,492
BEGIN DESCRIPTION:
OATMAN CREEK 114.0
END DESCRIPTION:
XS GIS Cut Line= 3
      2807455.66     10202903.11      2808463.47      10202995.1
       2809255.7      10202603.1
#Sta/Elev= 30
    3988 1277.21  4068.4 1272.51  4258.6 1263.94  4594.3 1261.94  4831.5 1261.85
  4861.6 1261.29  4881.7 1257.82  4891.8 1259.16    4925 1258.53    4942 1260.04
  4990.1 1256.93  4990.4 1256.43  4994.3 1256.93  5017.5 1261.05  5101.6  1260.2
    5114 1261.23  5203.3 1260.66  5270.2  1262.4  5303.5 1261.79  5376.4 1264.65
  5494.1 1266.97  5526.9 1270.74  5549.2 1269.08  5600.7 1271.72  5606.3 1271.16
  5623.1  1272.7  5718.4 1276.35  5757.7 1280.57    5825 1285.11  5883.9 1286.27
#Mann= 3 ,-1 , 0
    3988     .05       0  4990.1     .05       0  4994.3     .05       0
Bank Sta=4990.1,4994.3
XS Rating Curve= 0 ,0
Exp/Cntr=0.3,0.1