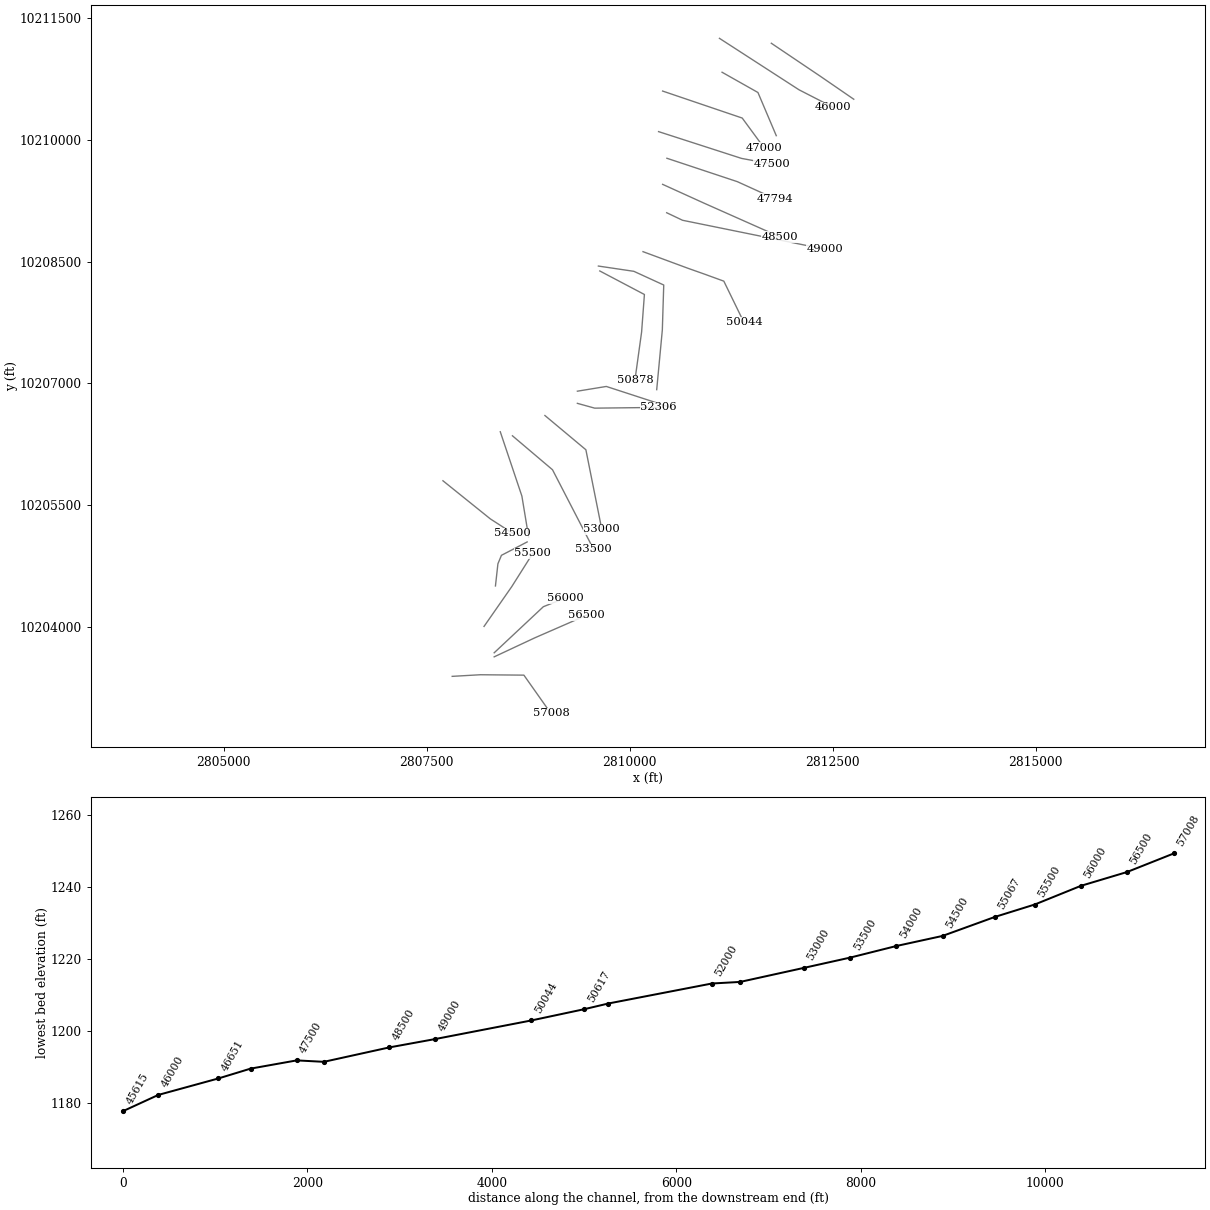
HEC-RAS study OATMAN CREEK.prj: OATMAN CREEK Base Level Engineering

--- OATMAN CREEK.g01 (geometry) --- (continued)

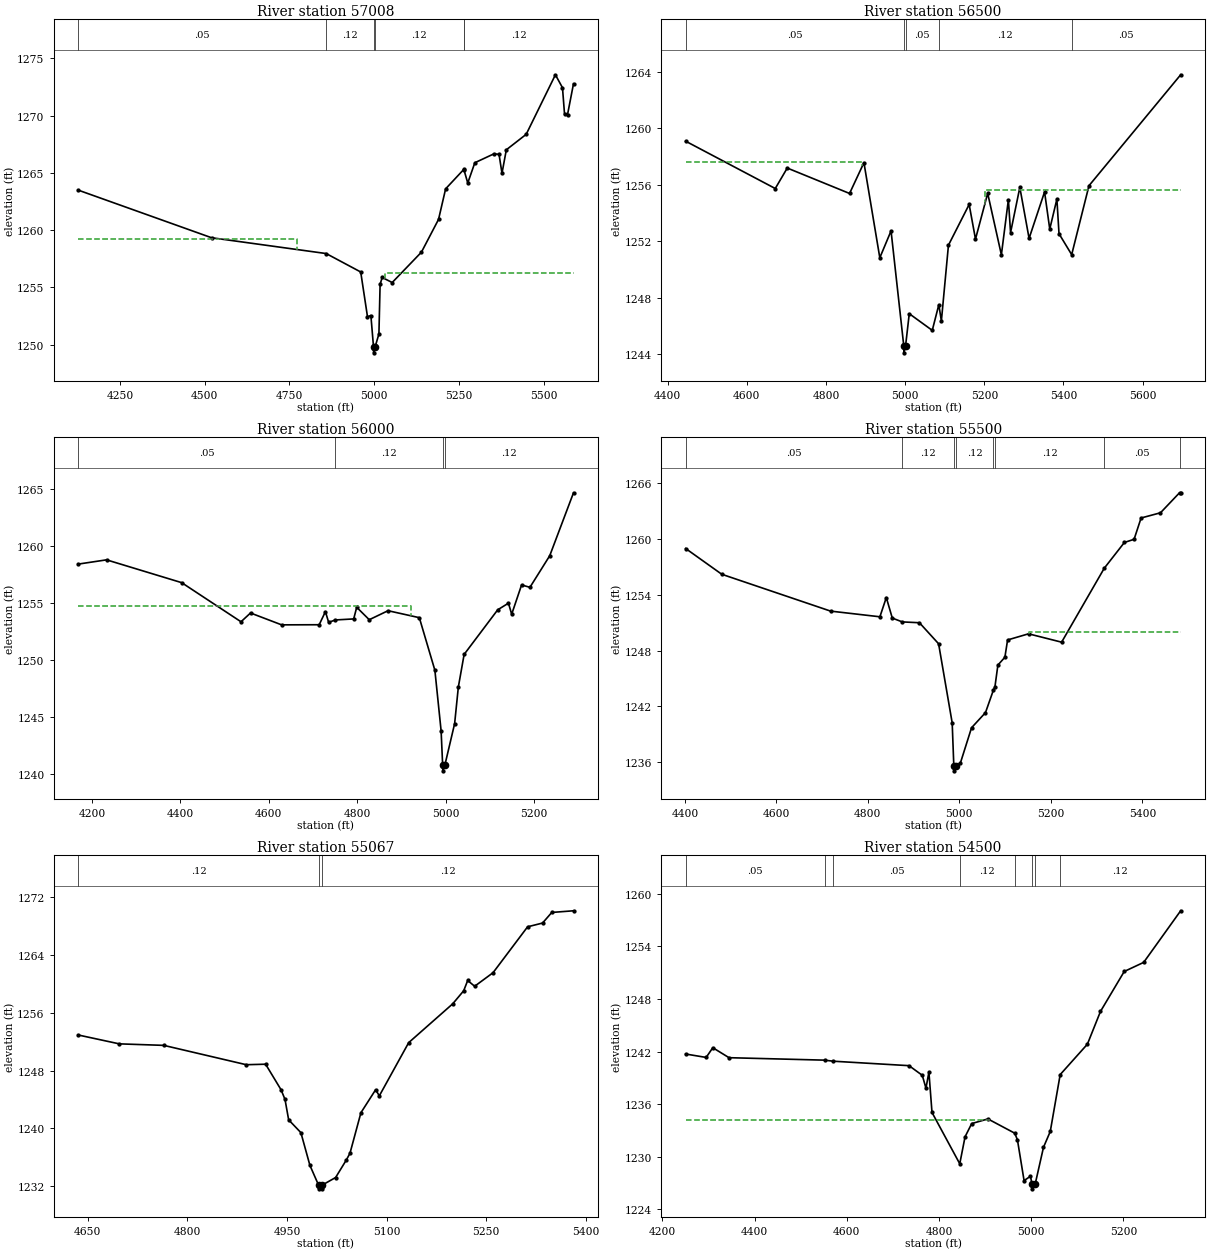
Type RM Length L Ch R = 1 ,57008   ,508,508,508
BEGIN DESCRIPTION:
Mapping XS 8b70ab02
END DESCRIPTION:
XS GIS Cut Line= 4
      2807813.54     10203387.59      2808160.89     10203407.44
      2808696.72     10203402.48      2809029.12     10202931.17
#Sta/Elev= 30
  4127.8 1263.48  4520.5 1259.33  4858.6 1257.95  4960.5 1256.34  4980.5 1252.43
  4990.5 1252.54  4998.3 1249.78  4998.6 1249.28  5002.8 1249.78  5014.2 1250.93
  5017.7 1255.26  5023.8 1255.86  5053.4 1255.42  5139.6 1258.07  5190.1 1260.93
    5211  1263.6  5264.4 1265.29  5265.4 1265.23  5276.3 1264.11  5297.2 1265.88
  5353.8 1266.66  5368.6 1266.61  5377.3 1264.96  5390.1 1267.01  5448.7 1268.36
  5534.9 1273.56  5555.8 1272.43  5561.9  1270.1  5570.6 1270.07  5588.3 1272.78
#Mann= 6 ,-1 , 0
  4127.8     .05       0  4858.6     .12       0  4998.3     .07       0
  5002.8     .12       0  5264.4     .05       0  5265.4     .12       0
#XS Ineff= 2 , 0
         4772.41 1259.19 5033.23         1256.21
Permanent Ineff=
       F       F
Bank Sta=4998.3,5002.8
XS Rating Curve= 0 ,0
Exp/Cntr=0.3,0.1

Type RM Length L Ch R = 1 ,56500   ,500,500,500
BEGIN DESCRIPTION:
OATMAN CREEK 112.0
END DESCRIPTION:
XS GIS Cut Line= 3
      2808330.68     10203628.11      2808832.87     10203863.23
      2809470.72     10204141.74
#Sta/Elev= 30
  4445.5 1259.08  4671.9 1255.73  4702.2 1257.18  4859.6 1255.38  4895.9 1257.56
    4936 1250.83  4964.4 1252.73  4996.5  1244.6  4996.8  1244.1  5001.1  1244.6
  5010.4 1246.87  5068.5 1245.69  5085.1 1247.51  5091.5 1246.35  5109.4 1251.72
  5161.7  1254.6  5177.7 1252.15  5208.5 1255.39  5243.1 1251.04  5260.8 1254.94
  5266.3 1252.61  5289.7 1255.81  5313.1  1252.2  5352.2 1255.49  5365.3 1252.86
  5383.3 1254.98  5388.7 1252.53  5420.7 1251.05  5464.4 1255.93    5696 1263.78
#Mann= 5 ,-1 , 0
  4445.5     .05       0  4996.5     .05       0  5001.1     .05       0
  5085.1     .12       0  5420.7     .05       0
#XS Ineff= 2 , 0
         4891.54  1257.6 5200.94         1255.66
Permanent Ineff=
       F       F
Bank Sta=4996.5,5001.1
XS Rating Curve= 0 ,0
Exp/Cntr=0.3,0.1

Type RM Length L Ch R = 1 ,56000   ,500,500,500
BEGIN DESCRIPTION:
OATMAN CREEK 111.0
END DESCRIPTION:
XS GIS Cut Line= 3
      2808330.66     10203678.09      2808936.63     10204246.31
       2809205.7     10204353.12
#Sta/Elev= 30
  4169.3 1258.39  4232.8 1258.76  4402.8 1256.76  4537.1 1253.33  4558.6  1254.1
    4629 1253.06    4714 1253.07  4728.1 1254.22  4735.4 1253.28  4750.6 1253.49
  4792.1 1253.58  4798.9  1254.6  4827.3 1253.51  4869.8  1254.3  4940.6 1253.69
  4975.8 1249.08  4989.9 1243.77  4993.4 1240.76  4993.8 1240.26  4998.4 1240.76
  5020.5  1244.4  5028.9 1247.61    5042 1250.47    5118 1254.38  5142.3 1254.96
  5149.6 1253.99    5172 1256.56  5190.9 1256.35  5235.7 1259.12  5289.5 1264.64
#Mann= 4 ,-1 , 0
  4169.3     .05       0  4750.6     .12       0  4993.4     .07       0
  4998.4     .12       0
#XS Ineff= 2 , 0
         4921.63 1254.71
Permanent Ineff=
       F       F
Bank Sta=4993.4,4998.4
XS Rating Curve= 0 ,0
Exp/Cntr=0.3,0.1

Type RM Length L Ch R = 1 ,55500   ,433,433,433
BEGIN DESCRIPTION:
OATMAN CREEK 110.0
END DESCRIPTION:
XS GIS Cut Line= 3
      2808205.67     10204003.09       2808547.4     10204494.07
       2808805.7     10204903.14
#Sta/Elev= 30
  4401.8 1258.97  4480.8  1256.2  4718.6 1252.24  4826.4 1251.63  4840.4  1253.7
  4853.5 1251.49  4875.3 1251.08  4912.8 1250.99  4954.7 1248.73  4984.4 1240.23
    4988 1235.57  4988.3 1235.07    4993 1235.57  5002.4 1235.92  5026.7  1239.7
  5057.2 1241.33  5074.5 1243.75  5077.9 1244.12  5084.3 1246.44  5099.6 1247.28
  5105.5 1249.14  5151.3  1249.8  5223.6  1248.9  5316.8 1256.85  5360.8 1259.62
    5382 1259.96  5397.3 1262.25  5439.7 1262.81  5481.3 1264.96  5483.8 1264.96
#Mann= 8 ,-1 , 0
  4401.8     .05       0  4875.3     .12       0    4988     .07       0
    4993     .12       0  5074.5     .05       0  5077.9     .12       0
  5316.8     .05       0  5481.3     .12       0
#XS Ineff= 2 , 0
                         5152.35            1250
Permanent Ineff=
       F       F
Bank Sta=4988,4993
XS Rating Curve= 0 ,0
Exp/Cntr=0.3,0.1

Type RM Length L Ch R = 1 ,55067   ,567,567,567
BEGIN DESCRIPTION:
Mapping XS 8bcd0dec
END DESCRIPTION:
XS GIS Cut Line= 4
      2808346.34     10204502.05      2808376.72     10204775.48
      2808420.12     10204879.65        2808737.      10205044.6
#Sta/Elev= 30
  4636.1 1252.92  4697.5  1251.7  4764.5 1251.49  4888.7 1248.81  4917.8 1248.88
  4941.1 1245.33    4947    1244  4952.5 1241.17  4970.9  1239.4  4984.5 1234.86
  4997.6 1232.11    4998 1231.61  5002.3 1231.61  5002.6 1232.11  5023.2 1233.18
  5039.2 1235.59  5044.8 1236.54  5061.3 1242.16  5083.4 1245.34    5089  1244.5
  5133.2 1251.87  5199.5 1257.25    5216 1259.06    5222 1260.48  5232.5 1259.68
  5260.2 1261.56  5312.2 1267.92  5334.7 1268.44  5348.6 1269.91  5381.3 1270.14
#Mann= 3 ,-1 , 0
  4636.1     .12       0  4997.6     .07       0  5002.6     .12       0
Bank Sta=4997.6,5002.6
XS Rating Curve= 0 ,0
Exp/Cntr=0.3,0.1

Type RM Length L Ch R = 1 ,54500   ,500,500,500
BEGIN DESCRIPTION:
OATMAN CREEK 108.0
END DESCRIPTION:
XS GIS Cut Line= 3
       2807699.5     10205798.83       2808283.4     10205328.76
      2808555.66     10205153.12
#Sta/Elev= 30
  4250.4 1241.72  4294.9 1241.33  4309.3 1242.44  4344.5  1241.3  4551.6 1241.02
  4570.1  1240.9  4734.9 1240.39  4763.6 1239.29  4771.6 1237.82    4778 1239.65
  4784.7 1235.05  4844.9 1229.19  4856.4 1232.27  4870.8 1233.78    4906 1234.31
  4964.2 1232.68    4970 1231.92  4984.4 1227.27  4998.3 1227.77  5001.6 1226.83
  5002.1 1226.33  5008.3 1226.83  5026.5 1231.07  5041.2 1232.88  5062.7 1239.37
  5121.7 1242.84  5150.1 1246.58  5201.6 1251.14  5243.8 1252.18    5324 1258.07
#Mann= 8 ,-1 , 0
  4250.4     .05       0  4551.6     .12       0  4570.1     .05       0
  4844.9     .12       0  4964.2     .05       0  5001.6     .05       0
  5008.3     .05       0  5062.7     .12       0
#XS Ineff= 2 , 0
         4910.97 1234.22
Permanent Ineff=
       F       F
Bank Sta=5001.6,5008.3
XS Rating Curve= 0 ,0
Exp/Cntr=0.3,0.1

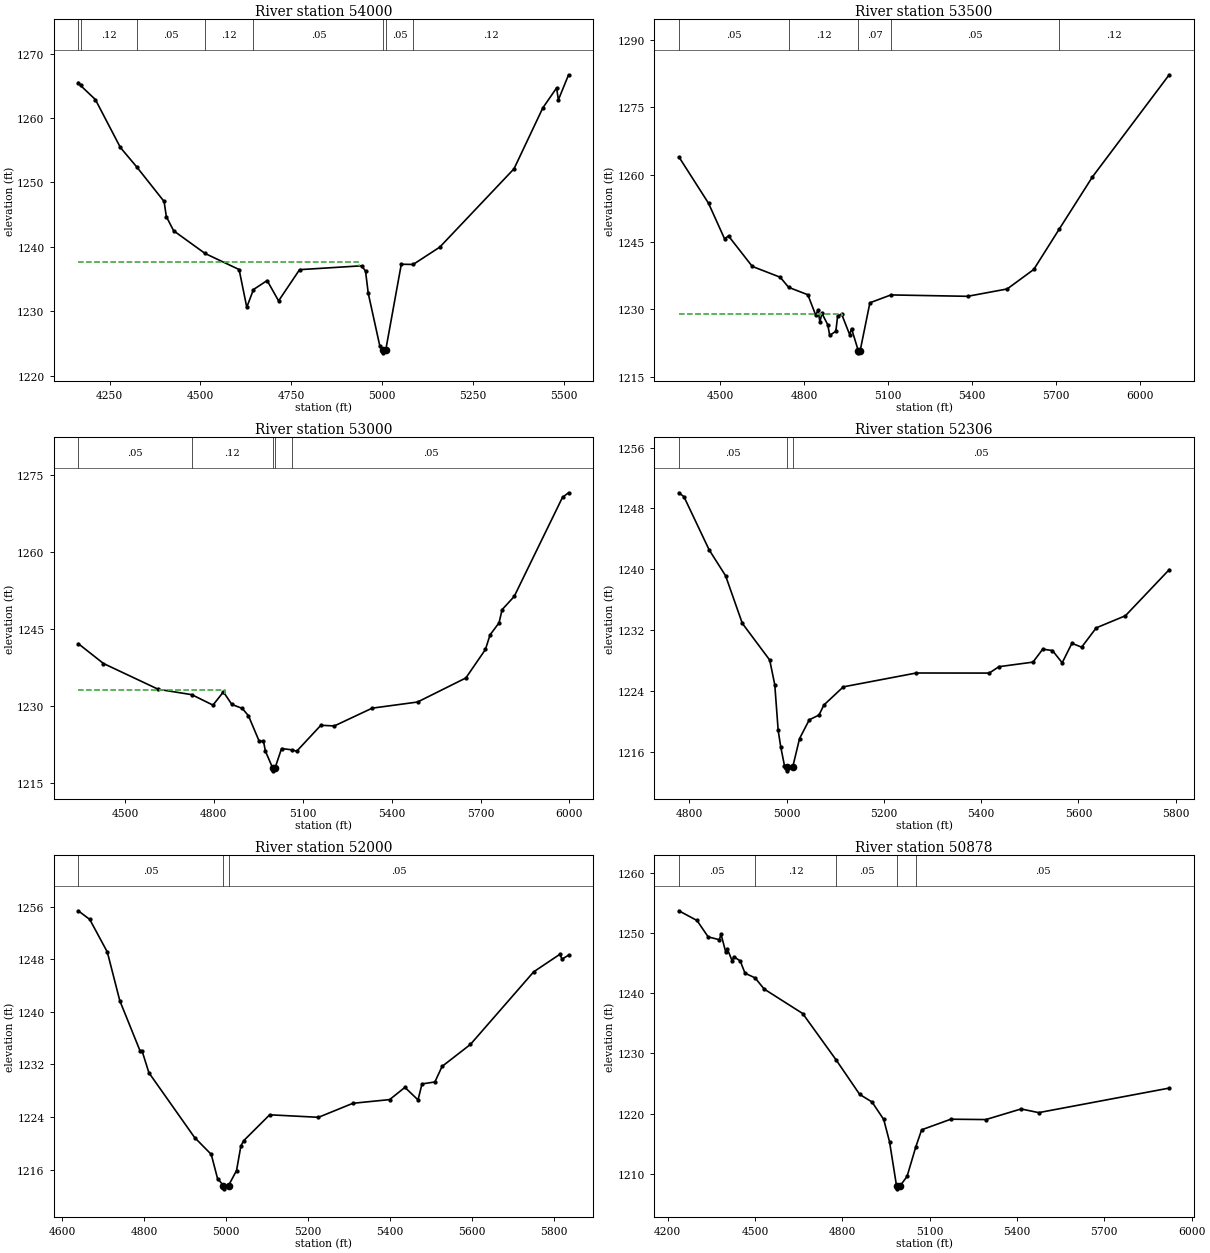
Type RM Length L Ch R = 1 ,54000   ,500,500,500
BEGIN DESCRIPTION:
OATMAN CREEK 107.0
END DESCRIPTION:
XS GIS Cut Line= 3
       2808405.7     10206403.07      2808671.96     10205610.07
      2808755.68     10205103.14
#Sta/Elev= 30
  4163.5 1265.52  4169.8 1265.06  4210.7 1262.87  4279.5 1255.43  4325.5 1252.34
  4399.9 1247.04  4406.1 1244.69  4426.2 1242.49  4512.9 1238.96  4606.5 1236.47
  4627.6 1230.61    4646 1233.36  4683.7 1234.76  4715.2  1231.6    4773 1236.45
  4944.1 1237.05  4954.6 1236.23  4962.2 1232.76  4993.8 1224.64  5003.6 1224.03
  5004.1 1223.53  5010.5 1224.03  5053.1 1237.29  5085.8 1237.26  5159.1 1239.95
  5363.6 1252.12  5442.9 1261.58  5480.7 1264.67  5485.8 1262.84  5513.8 1266.72
#Mann= 8 ,-1 , 0
  4163.5     .05       0  4169.8     .12       0  4325.5     .05       0
  4512.9     .12       0    4646     .05       0  5003.6     .05       0
  5010.5     .05       0  5085.8     .12       0
#XS Ineff= 2 , 0
         4935.42  1237.6
Permanent Ineff=
       F       F
Bank Sta=5003.6,5010.5
XS Rating Curve= 0 ,0
Exp/Cntr=0.3,0.1

Type RM Length L Ch R = 1 ,53500   ,500,500,500
BEGIN DESCRIPTION:
OATMAN CREEK 106.0
END DESCRIPTION:
XS GIS Cut Line= 3
      2808555.72     10206353.08      2809049.16      10205934.6
      2809555.69      10204953.1
#Sta/Elev= 30
    4353 1263.93  4458.9 1253.61  4516.1 1245.71  4530.4 1246.32  4615.2 1239.55
  4714.9 1237.14  4745.4 1234.88  4813.7 1233.24  4842.3 1228.63    4850 1229.94
  4856.6 1227.23  4864.3 1229.08  4885.2 1226.51  4891.7 1224.18  4913.7 1225.11
  4920.3 1228.56  4934.6  1228.9  4963.2 1224.35  4969.7 1225.72  4993.8 1220.81
  4994.3 1220.31  5000.7 1220.81  5035.4 1231.45  5110.5  1233.2  5384.3 1232.89
  5525.8 1234.53  5620.6 1238.86  5710.9 1247.77  5830.4 1259.48  6104.5  1282.2
#Mann= 5 ,-1 , 0
    4353     .05       0  4745.4     .12       0  4993.8     .07       0
  5110.5     .05       0  5710.9     .12       0
#XS Ineff= 2 , 0
         4936.52 1228.97
Permanent Ineff=
       F       F
Bank Sta=4993.8,5000.7
XS Rating Curve= 0 ,0
Exp/Cntr=0.3,0.1

Type RM Length L Ch R = 1 ,53000   ,694,694,694
BEGIN DESCRIPTION:
OATMAN CREEK 105.0
END DESCRIPTION:
XS GIS Cut Line= 3
       2808955.7      10206603.1      2809460.28     10206181.08
      2809655.69     10205203.11
#Sta/Elev= 30
  4342.2  1242.2  4427.4 1238.33  4612.2 1233.32  4725.5 1232.27    4797 1230.24
  4832.1 1232.81  4860.7 1230.37  4895.9  1229.6  4916.7 1228.17  4953.1  1223.2
  4967.4 1223.25  4973.9 1221.29  4998.9 1217.96  4999.4 1217.46  5006.2 1217.96
  5028.5  1221.8  5064.9 1221.53  5079.5 1221.27  5161.1 1226.32  5206.6 1226.19
  5334.4 1229.65  5487.4 1230.84  5650.6 1235.52  5716.7 1241.07  5732.2  1243.9
  5762.6 1246.24  5772.9  1248.8  5813.7 1251.37  5976.9 1270.66  5997.3 1271.53
#Mann= 5 ,-1 , 0
  4342.2     .05       0  4725.5     .12       0  4998.9     .07       0
  5006.2     .12       0  5064.9     .05       0
#XS Ineff= 2 , 0
         4837.62 1233.25
Permanent Ineff=
       F       F
Bank Sta=4998.9,5006.2
XS Rating Curve= 0 ,0
Exp/Cntr=0.3,0.1

Type RM Length L Ch R = 1 ,52306   ,306,306,306
BEGIN DESCRIPTION:
OATMAN CREEK 104.0
END DESCRIPTION:
XS GIS Cut Line= 3
      2809355.64     10206753.12        2809569.       10206694.
      2810355.65     10206703.11
#Sta/Elev= 30
  4778.6 1250.06    4789 1249.55  4840.9 1242.56  4874.7 1239.16    4909 1232.92
  4965.4 1228.09  4975.8 1224.84  4982.8 1218.85    4988 1216.71  4995.7 1214.22
  5000.6 1214.04  5001.1 1213.54  5012.7 1214.04  5026.7 1217.77  5046.7 1220.24
  5066.7 1220.87  5076.7 1222.18  5116.7 1224.57  5266.7 1226.39  5416.7 1226.38
  5436.7 1227.22  5506.7 1227.82  5526.7 1229.52  5546.7 1229.34  5566.7 1227.73
  5586.7 1230.29  5606.7 1229.78  5636.7 1232.32  5696.7 1233.91  5786.7 1239.96
#Mann= 3 ,-1 , 0
  4778.6     .05       0  5000.6     .05       0  5012.7     .05       0
Bank Sta=5000.6,5012.7
XS Rating Curve= 0 ,0
Exp/Cntr=0.3,0.1

Type RM Length L Ch R = 1 ,52000   ,1122,1122,1122
BEGIN DESCRIPTION:
OATMAN CREEK 103.0
END DESCRIPTION:
XS GIS Cut Line= 3
      2809355.69     10206903.11      2809711.83      10206961.5
      2810505.64     10206703.13
#Sta/Elev= 30
  4639.1 1255.35  4667.2 1254.03    4710 1249.08  4740.4 1241.69  4789.8 1234.07
  4794.9 1234.02  4811.4 1230.74  4922.8  1220.9  4963.4 1218.34  4978.8 1214.66
  4993.3  1213.6  4993.8  1213.1  5005.6  1213.6  5025.1 1215.88  5035.6 1219.58
  5042.1 1220.39  5105.9 1224.35  5224.9 1223.97    5309  1226.1  5398.5 1226.66
  5435.7 1228.52  5467.7 1226.61  5477.3 1229.04  5508.8 1229.34  5526.3  1231.7
  5595.4 1235.04  5749.8 1246.08  5813.6 1248.74  5818.9    1248  5834.8 1248.61
#Mann= 3 ,-1 , 0
  4639.1     .05       0  4993.3     .05       0  5005.6     .05       0
Bank Sta=4993.3,5005.6
XS Rating Curve= 0 ,0
Exp/Cntr=0.3,0.1

Type RM Length L Ch R = 1 ,50878   ,261,261,261
BEGIN DESCRIPTION:
Mapping XS e5de1343
END DESCRIPTION:
XS GIS Cut Line= 4
      2809631.65     10208385.15      2810181.36     10208095.15
      2810146.73     10207632.01      2810064.49     10207039.03
#Sta/Elev= 30
  4238.2 1253.66  4300.5 1252.05  4338.9 1249.33  4377.3 1248.86    4383 1249.79
  4399.3 1246.79    4405 1247.31  4421.4 1245.33    4427 1246.05    4449 1245.34
  4465.4 1243.31    4500 1242.53  4531.5 1240.67  4663.6 1236.62    4779 1228.89
  4859.3 1223.21  4901.9 1221.94    4942 1219.05    4962 1215.35    4986 1208.04
  4986.5 1207.54  4998.3 1208.04  5022.2  1209.6  5052.3 1214.51  5072.3 1217.33
  5172.6 1219.09    5293 1219.03  5413.9 1220.79  5474.5 1220.18  5922.8 1224.25
#Mann= 5 ,-1 , 0
  4238.2     .05       0    4500     .12       0    4779     .05       0
    4986     .05       0  5052.3     .05       0
Bank Sta=4986,4998.3
XS Rating Curve= 0 ,0
Exp/Cntr=0.3,0.1

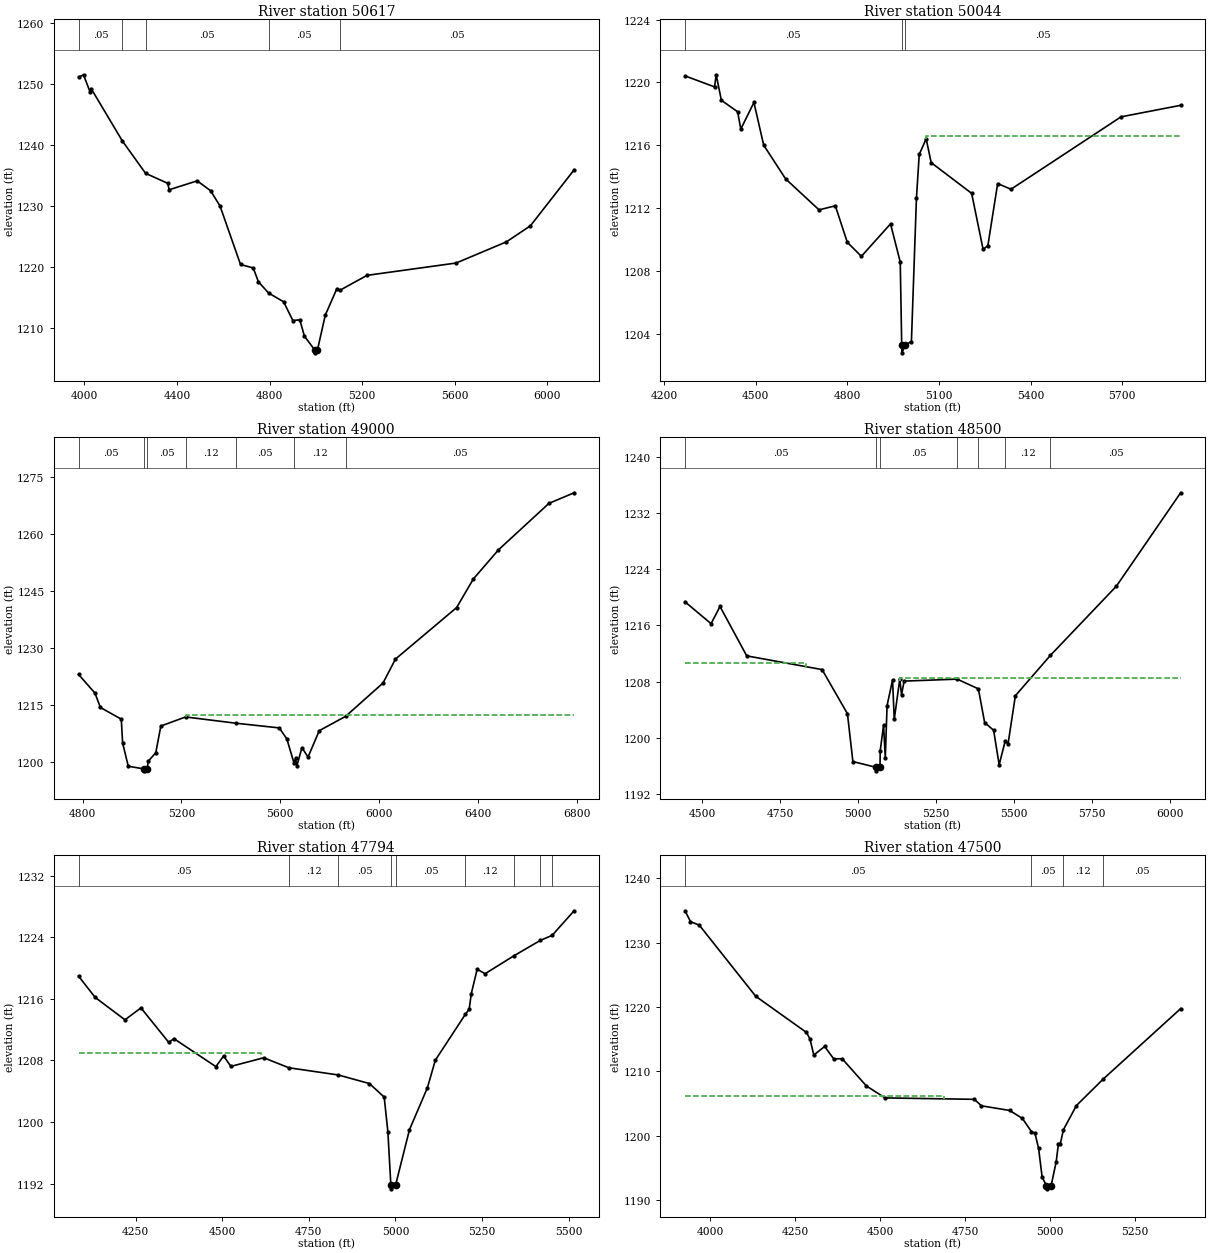
Type RM Length L Ch R = 1 ,50617   ,573,573,573
BEGIN DESCRIPTION:
Mapping XS 22f8193e
END DESCRIPTION:
XS GIS Cut Line= 5
      2809614.32     10208445.75       2810051.5     10208380.82
      2810419.42     10208212.01       2810402.1     10207657.98
      2810332.84     10206922.11
#Sta/Elev= 30
  3975.2 1251.11  3996.8  1251.5  4024.6 1248.74  4029.7 1249.24  4164.4 1240.67
  4264.8 1235.36  4360.8 1233.72  4366.7 1232.67  4487.8 1234.13  4545.9  1232.5
  4586.4    1230  4674.8 1220.43  4729.8 1219.86  4751.9 1217.61  4795.9 1215.76
  4860.9 1214.32  4900.9 1211.25  4930.9 1211.37  4950.9 1208.68  4994.8 1206.46
  4995.3 1205.96  5007.2 1206.46    5041 1212.15    5091 1216.47  5103.8  1216.2
  5221.1 1218.65    5606 1220.67  5823.2 1224.14  5926.8 1226.77  6115.4 1235.93
#Mann= 5 ,-1 , 0
  3975.2     .05       0  4164.4     .12       0  4264.8     .05       0
  4795.9     .05       0  5103.8     .05       0
Bank Sta=4994.8,5007.2
XS Rating Curve= 0 ,0
Exp/Cntr=0.3,0.1

Type RM Length L Ch R = 1 ,50044   ,1044,1044,1044
BEGIN DESCRIPTION:
Mapping XS 586afb12
END DESCRIPTION:
XS GIS Cut Line= 5
      2810164.09     10208623.19      2810713.75     10208419.78
      2810921.51     10208346.19      2811159.57     10208259.63
      2811406.27     10207753.24
#Sta/Elev= 30
  4268.1 1220.42  4364.8 1219.72  4370.1 1220.49  4387.1 1218.87  4440.4 1218.14
  4450.7 1217.04  4493.7 1218.73  4525.7 1216.02  4597.4 1213.88    4707 1211.91
  4760.3 1212.17  4799.5 1209.85  4845.6 1208.96  4941.1 1211.02  4972.9  1208.6
  4977.7 1203.33  4978.2 1202.83  4990.1 1203.33  5009.5 1203.55    5026 1212.68
  5035.1 1215.43  5057.8 1216.42  5074.2 1214.91  5206.7 1212.96  5244.3  1209.4
  5259.9 1209.64  5291.9 1213.58  5335.6 1213.22  5696.2 1217.82  5891.2 1218.55
#Mann= 3 ,-1 , 0
  4268.1     .05       0  4977.7     .05       0  4990.1     .05       0
#XS Ineff= 2 , 0
                         5057.68         1216.61
Permanent Ineff=
       F       F
Bank Sta=4977.7,4990.1
XS Rating Curve= 0 ,0
Exp/Cntr=0.3,0.1

Type RM Length L Ch R = 1 ,49000   ,500,500,500
BEGIN DESCRIPTION:
OATMAN CREEK 97.0
END DESCRIPTION:
XS GIS Cut Line= 3
      2810455.65     10209103.13      2810651.47     10209010.07
      2812405.72      10208653.1
#Sta/Elev= 30
  4783.2 1223.08  4849.7 1218.15  4871.8 1214.36  4956.4 1211.27  4961.9 1204.97
  4984.7 1198.87  5048.8 1198.15  5049.3 1197.65  5061.3 1198.15  5065.5 1200.17
  5096.1 1202.43  5116.6 1209.46  5216.8 1211.86  5420.1 1210.21  5596.2 1208.97
  5626.8 1206.08    5656 1199.68  5662.1 1200.95  5667.6 1198.98    5688 1203.76
  5712.7 1201.29  5758.2 1208.24  5864.9 1212.02  6016.3  1220.8  6066.8 1227.12
  6314.7 1240.71    6382 1248.22    6484 1255.92  6688.1 1268.16  6790.2 1270.96
#Mann= 7 ,-1 , 0
  4783.2     .05       0  5048.8     .05       0  5061.3     .05       0
  5216.8     .12       0  5420.1     .05       0    5656     .12       0
  5864.9     .05       0
#XS Ineff= 2 , 0
                         5217.08         1212.26
Permanent Ineff=
       F       F
Bank Sta=5048.8,5061.3
XS Rating Curve= 0 ,0
Exp/Cntr=0.3,0.1

Type RM Length L Ch R = 1 ,48500   ,706,706,706
BEGIN DESCRIPTION:
OATMAN CREEK 96.0
END DESCRIPTION:
XS GIS Cut Line= 3
      2810405.64     10209453.13      2810910.24     10209223.71
       2811855.7      10208803.1
#Sta/Elev= 30
  4445.7 1219.36  4529.2 1216.25  4557.8  1218.7  4643.5 1211.67  4885.1 1209.72
  4966.4 1203.44  4983.9 1196.63  5058.3 1195.81  5058.8 1195.31  5070.8 1195.81
  5071.6  1198.2  5082.3 1201.81  5087.8 1197.15  5093.5 1204.58  5111.1 1208.25
  5116.5 1202.62  5134.3 1208.39  5139.8 1206.12  5148.2 1208.08  5318.2 1208.36
  5386.2 1206.98  5406.4 1202.18  5435.2 1201.08  5452.9 1196.18  5471.9 1199.49
  5481.6 1199.19  5504.9    1206    5617 1211.73    5829  1221.6  6034.8 1234.88
#Mann= 7 ,-1 , 0
  4445.7     .05       0  5058.3     .05       0  5070.8     .05       0
  5318.2     .12       0  5386.2     .05       0  5471.9     .12       0
    5617     .05       0
#XS Ineff= 2 , 0
         4834.48 1210.67 5133.54         1208.59
Permanent Ineff=
       F       F
Bank Sta=5058.3,5070.8
XS Rating Curve= 0 ,0
Exp/Cntr=0.3,0.1

Type RM Length L Ch R = 1 ,47794   ,294,294,294
BEGIN DESCRIPTION:
OATMAN CREEK 95.0
END DESCRIPTION:
XS GIS Cut Line= 3
       2810458.4     10209774.55       2811326.5       10209486.
      2811795.81     10209272.48
#Sta/Elev= 30
  4085.2 1218.95  4133.5 1216.17  4219.3 1213.27  4265.4 1214.82  4345.8 1210.33
  4360.4 1210.83  4481.8 1207.19  4503.9 1208.58  4524.9 1207.22  4619.8 1208.34
  4692.5 1207.04  4834.7 1206.11    4925 1204.99  4967.5 1203.23  4978.1 1198.73
  4986.7 1191.82  4987.2 1191.32  5000.4 1191.82  5040.4    1199    5092 1204.42
  5115.1 1208.03  5201.7 1213.98  5212.8 1214.65  5218.8 1216.66  5235.8 1219.83
  5258.9 1219.26  5341.7 1221.58  5418.5 1223.59  5452.3 1224.24  5515.6 1227.43
#Mann= 9 ,-1 , 0
  4085.2     .05       0  4692.5     .12       0  4834.7     .05       0
  4986.7     .05       0  5000.4     .05       0  5201.7     .12       0
  5341.7     .05       0  5418.5     .12       0  5452.3     .05       0
#XS Ineff= 2 , 0
         4611.91 1208.92
Permanent Ineff=
       F       F
Bank Sta=4986.7,5000.4
XS Rating Curve= 0 ,0
Exp/Cntr=0.3,0.1

Type RM Length L Ch R = 1 ,47500   ,500,500,500
BEGIN DESCRIPTION:
OATMAN CREEK 94.0
END DESCRIPTION:
XS GIS Cut Line= 3
      2810355.72      10210103.1      2811377.89     10209772.82
      2811755.71     10209703.11
#Sta/Elev= 30
  3925.8 1234.96  3941.8 1233.28  3967.8 1232.72  4133.9 1221.66  4283.1 1216.04
  4293.6 1215.01  4304.6 1212.52  4336.6 1213.86  4363.4 1211.93  4388.2 1211.95
  4459.4 1207.72  4514.3 1205.86    4777 1205.64    4798 1204.63    4881 1203.91
  4918.3 1202.68  4945.1 1200.63  4955.6 1200.35  4966.2    1198  4976.7 1193.52
  4989.4 1192.22  4989.9 1191.72  5003.1 1192.22  5018.1 1195.96  5024.6 1198.76
  5029.7 1198.63  5039.3 1200.91  5077.5 1204.67  5155.6 1208.75  5384.2 1219.74
#Mann= 4 ,-1 , 0
  3925.8     .05       0  4945.1     .05       0  5039.3     .12       0
  5155.6     .05       0
#XS Ineff= 2 , 0
         4687.77 1206.16
Permanent Ineff=
       F       F
Bank Sta=4989.4,5003.1
XS Rating Curve= 0 ,0
Exp/Cntr=0.3,0.1

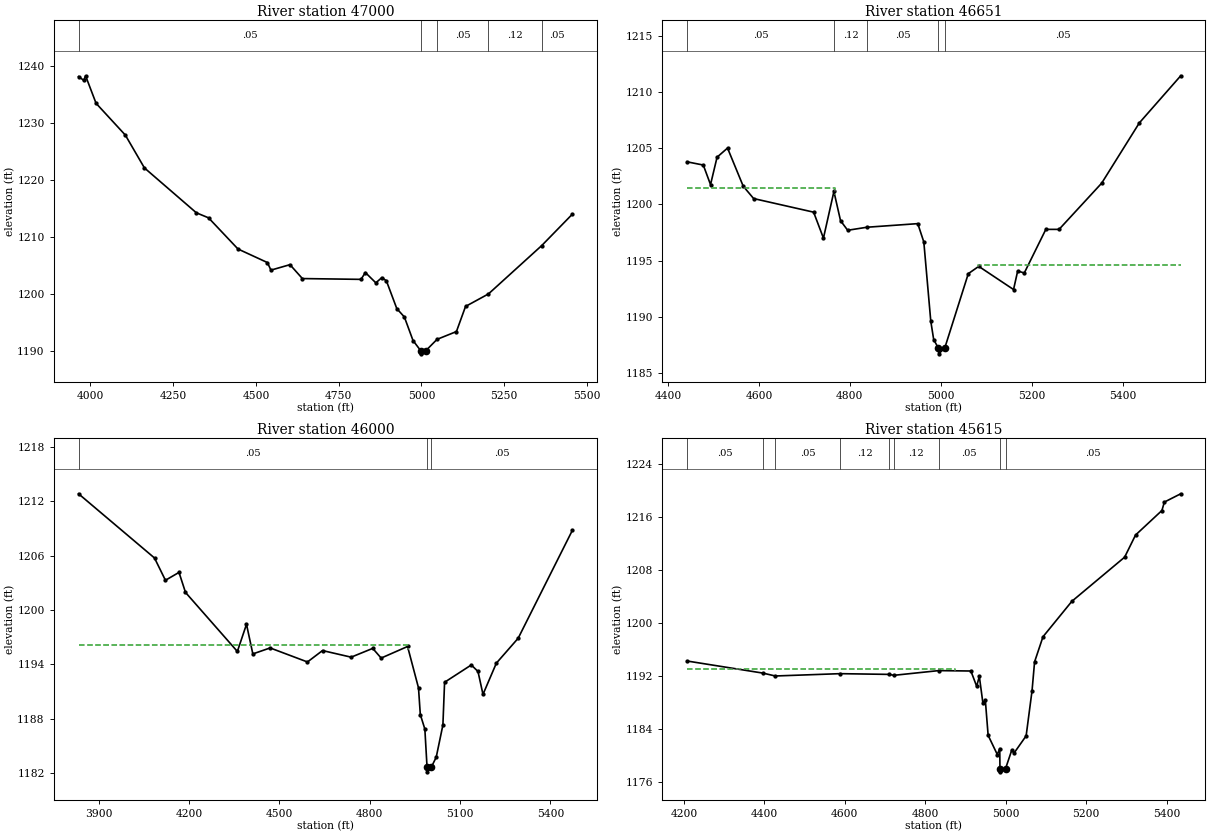
Type RM Length L Ch R = 1 ,47000   ,349,349,349
BEGIN DESCRIPTION:
OATMAN CREEK 93.0
END DESCRIPTION:
XS GIS Cut Line= 3
      2810405.64     10210603.13       2811386.2     10210270.32
      2811655.69      10209903.1
#Sta/Elev= 30
  3964.5 1238.09  3980.2 1237.43  3985.7 1238.23  4017.4  1233.4  4105.8 1227.82
  4163.4 1222.06  4320.3 1214.18    4357  1213.3  4445.9 1207.83  4534.8 1205.45
  4545.4 1204.12  4602.9 1205.08  4640.4 1202.64  4817.4  1202.5  4830.5  1203.7
  4862.2 1201.89  4880.2 1202.81  4893.9 1202.26  4925.5 1197.36  4948.3  1195.9
  4974.4 1191.77  4998.3 1189.93  4998.8 1189.43  5012.1 1189.93  5046.9 1191.97
  5105.5 1193.34    5133 1197.75  5202.1 1199.94    5363 1208.43  5455.5 1213.94
#Mann= 5 ,-1 , 0
  3964.5     .05       0  4998.3     .05       0  5046.9     .05       0
  5202.1     .12       0    5363     .05       0
Bank Sta=4998.3,5012.1
XS Rating Curve= 0 ,0
Exp/Cntr=0.3,0.1

Type RM Length L Ch R = 1 ,46651   ,651,651,651
BEGIN DESCRIPTION:
OATMAN CREEK 92.0
END DESCRIPTION:
XS GIS Cut Line= 3
      2811137.93     10210835.02      2811579.89     10210585.35
       2811805.7     10210053.07
#Sta/Elev= 30
  4441.7 1203.78  4477.7 1203.49  4493.6 1201.75    4508 1204.19    4531    1205
  4565.5 1201.61  4588.4 1200.51  4720.3  1199.3  4741.9 1196.99  4764.9 1201.14
  4779.5 1198.54  4795.2 1197.69  4837.7 1197.96  4949.3 1198.28  4962.6 1196.65
  4977.9 1189.61  4984.3 1187.97  4994.7  1187.2  4995.2  1186.7  5008.5  1187.2
  5060.4 1193.83  5083.4 1194.48  5159.9 1192.42    5169 1194.07  5183.5 1193.89
  5230.9 1197.77    5260 1197.77  5353.7 1201.88  5436.5 1207.24  5527.5 1211.43
#Mann= 5 ,-1 , 0
  4441.7     .05       0  4764.9     .12       0  4837.7     .05       0
  4994.7     .05       0  5008.5     .05       0
#XS Ineff= 2 , 0
         4766.77 1201.46 5082.76         1194.58
Permanent Ineff=
       F       F
Bank Sta=4994.7,5008.5
XS Rating Curve= 0 ,0
Exp/Cntr=0.3,0.1

Type RM Length L Ch R = 1 ,46000   ,385,385,385
BEGIN DESCRIPTION:
OATMAN CREEK 91.0
END DESCRIPTION:
XS GIS Cut Line= 3
      2811105.72     10211253.09      2812085.24     10210619.09
      2812505.71      10210403.1
#Sta/Elev= 30
  3833.2 1212.82  4085.4 1205.73  4121.7 1203.27  4166.7 1204.14  4188.3 1201.93
  4360.5 1195.41  4390.8 1198.41  4411.9 1195.14  4469.3  1195.8  4593.2 1194.25
  4643.2 1195.51  4738.3 1194.78  4809.9 1195.75  4837.9 1194.68  4925.6 1195.96
  4961.9 1191.39  4967.9 1188.45    4983 1186.84  4990.3 1182.62  4990.8 1182.12
  5004.2 1182.62  5020.7 1183.73  5042.9 1187.29  5048.5 1192.01  5137.2 1193.92
  5159.4  1193.2    5176 1190.67  5220.4 1194.12  5292.8 1196.87  5472.7 1208.78
#Mann= 3 ,-1 , 0
  3833.2     .05       0  4990.3     .05       0  5004.2     .05       0
#XS Ineff= 2 , 0
         4928.53 1196.17
Permanent Ineff=
       F       F
Bank Sta=4990.3,5004.2
XS Rating Curve= 0 ,0
Exp/Cntr=0.3,0.1

Type RM Length L Ch R = 1 ,45615   ,615,615,615
BEGIN DESCRIPTION:
Mapping XS 27dd47e4
END DESCRIPTION:
XS GIS Cut Line= 3
      2811744.69     10211192.42      2812343.66     10210788.77
       2812760.3     10210502.33
#Sta/Elev= 30
  4207.4 1194.28  4396.8 1192.45    4427 1192.02  4588.2 1192.37  4710.9 1192.26
  4721.9 1192.12  4833.5 1192.83  4913.5 1192.77  4927.9 1190.47  4934.5 1191.96
  4943.4 1187.94  4949.4  1188.4  4956.4 1183.08  4979.2 1180.19  4985.3 1181.09
  4985.8 1178.08  4986.3 1177.58  4999.8 1178.08  5015.1 1180.84  5021.1 1180.43
  5050.9    1183  5065.6 1189.81  5071.9 1194.15  5092.8 1197.93  5164.6 1203.27
  5295.8 1209.92  5322.9 1213.25  5388.5 1216.95  5394.6 1218.22  5435.3 1219.47
#Mann= 9 ,-1 , 0
  4207.4     .05       0  4396.8     .12       0    4427     .05       0
  4588.2     .12       0  4710.9     .05       0  4721.9     .12       0
  4833.5     .05       0  4985.8     .05       0  4999.8     .05       0
#XS Ineff= 2 , 0
         4873.67  1193.1
Permanent Ineff=
       F       F
Bank Sta=4985.8,4999.8
XS Rating Curve= 0 ,0
Exp/Cntr=0.3,0.1