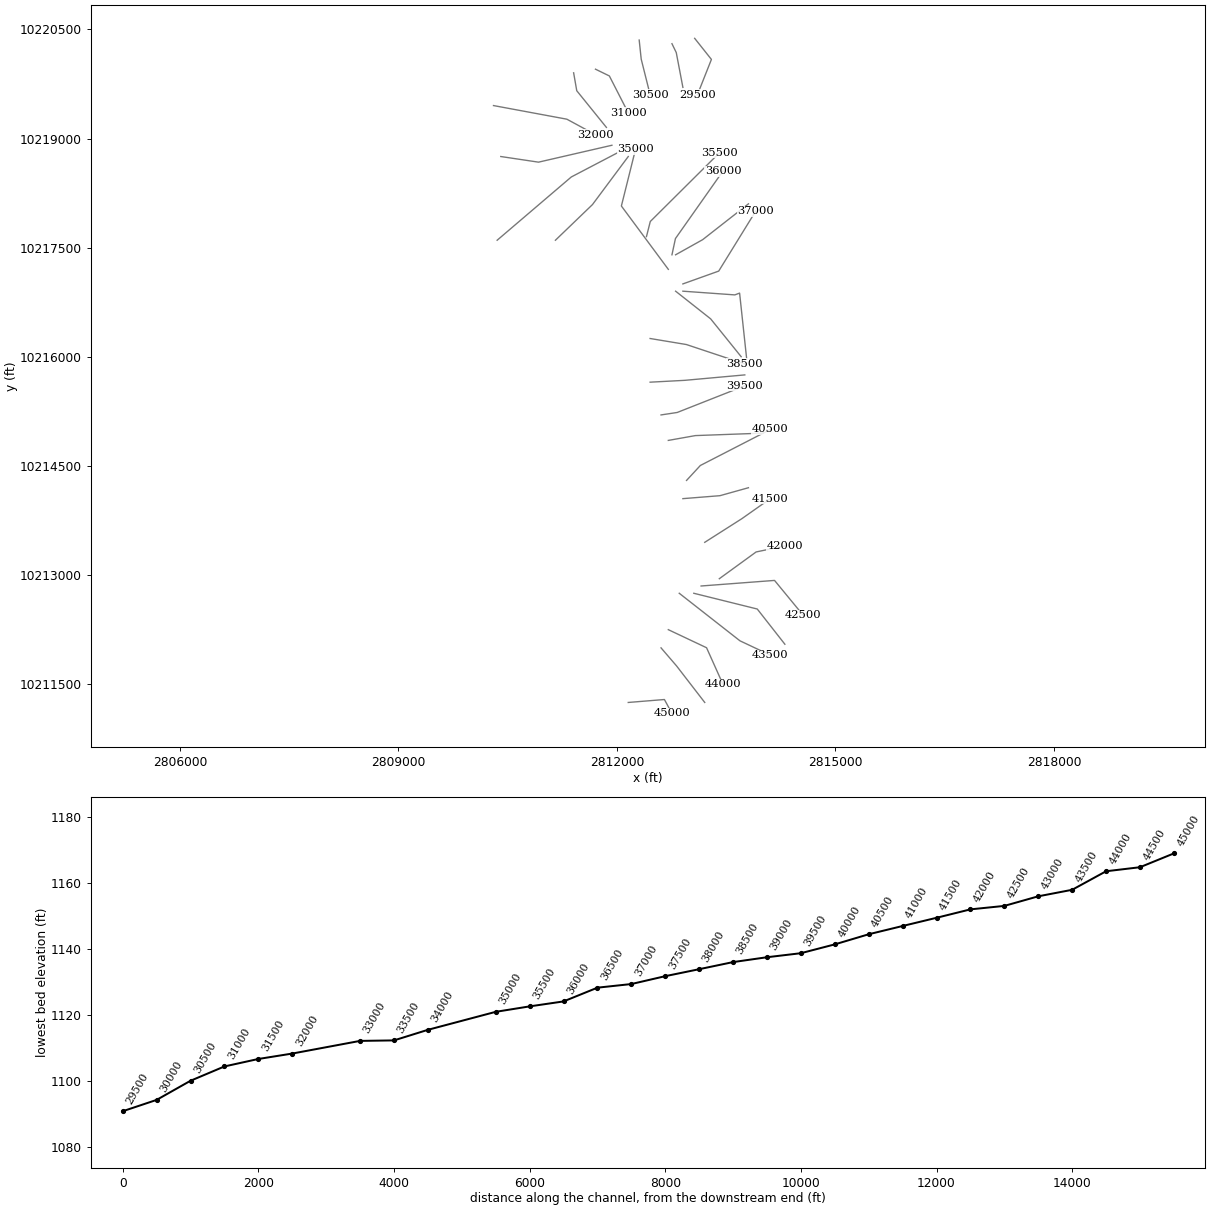
HEC-RAS study OATMAN CREEK.prj: OATMAN CREEK Base Level Engineering

--- OATMAN CREEK.g01 (geometry) --- (continued)

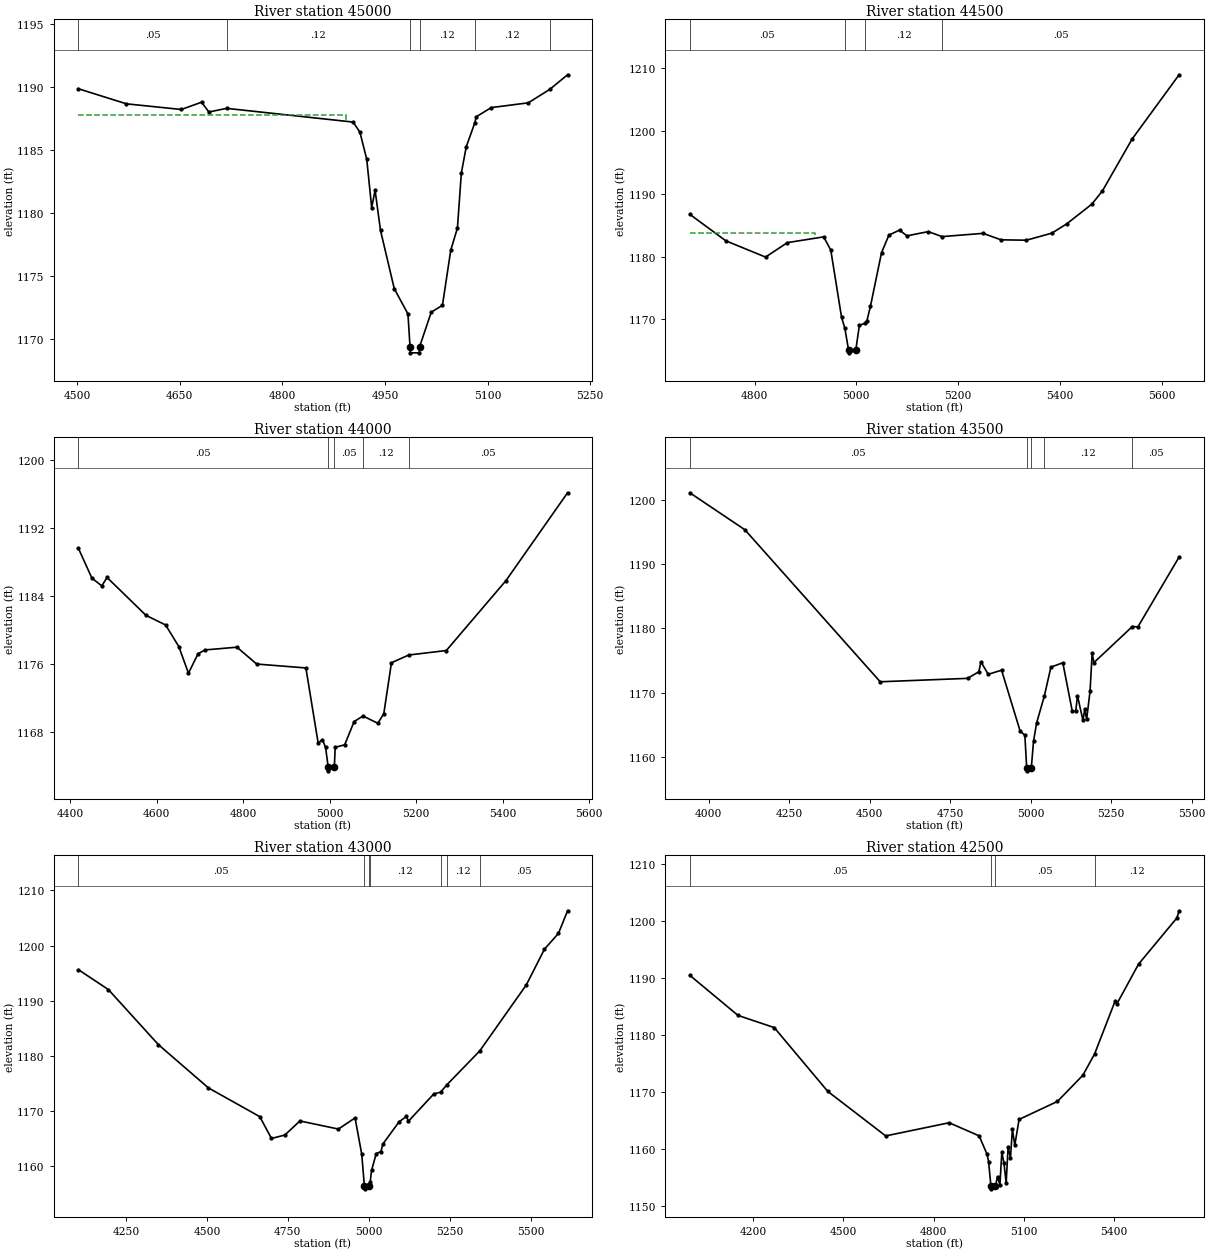
Type RM Length L Ch R = 1 ,45000   ,500,500,500
BEGIN DESCRIPTION:
OATMAN CREEK 89.0
END DESCRIPTION:
XS GIS Cut Line= 3
      2812155.66     10211253.11      2812652.01     10211293.57
      2812755.66     10211103.16
#Sta/Elev= 30
    4502 1189.86  4572.3 1188.66  4652.5 1188.21  4682.1 1188.79  4692.7 1188.01
  4718.7  1188.3  4903.4 1187.21  4913.4 1186.41  4923.4 1184.24  4930.6 1180.41
  4935.6 1181.78  4943.5 1178.59  4963.6 1173.96  4983.6 1171.95  4986.6 1169.36
  4987.1 1168.86  5000.2 1168.86  5000.7 1169.36  5017.6 1172.09    5034 1172.64
  5046.1 1177.01  5055.9 1178.79  5061.6 1183.16  5068.8 1185.25  5081.4 1187.17
  5083.4 1187.63  5105.2 1188.36  5159.4 1188.74  5190.8 1189.81  5216.8 1190.97
#Mann= 6 ,-1 , 0
    4502     .05       0  4718.7     .12       0  4986.6     .05       0
  5000.7     .12       0  5081.4     .12       0  5190.8     .05       0
#XS Ineff= 2 , 0
         4893.73  1187.8
Permanent Ineff=
       F       F
Bank Sta=4986.6,5000.7
XS Rating Curve= 0 ,0
Exp/Cntr=0.3,0.1

Type RM Length L Ch R = 1 ,44500   ,500,500,500
BEGIN DESCRIPTION:
OATMAN CREEK 88.0
END DESCRIPTION:
XS GIS Cut Line= 3
      2812605.71     10212003.08      2812818.76       10211755.
      2813205.67     10211253.13
#Sta/Elev= 30
    4673 1186.75  4743.7 1182.53  4821.7 1179.94  4864.5 1182.24  4935.8 1183.16
  4949.8 1181.06  4970.9 1170.36  4977.5 1168.56  4984.6 1165.18  4985.1 1164.68
    4999 1165.18  5005.9 1169.04  5016.9  1169.4  5020.4 1169.68  5027.6 1172.07
  5049.4 1180.63  5063.9 1183.44  5084.8 1184.24  5099.3 1183.32  5141.3    1184
  5168.2  1183.2  5248.7 1183.72    5284 1182.69  5333.9 1182.63  5383.7 1183.75
  5412.7 1185.21  5462.5 1188.38  5483.3  1190.5  5541.3 1198.73  5633.7 1208.99
#Mann= 4 ,-1 , 0
    4673     .05       0  4977.5     .05       0  5016.9     .12       0
  5168.2     .05       0
#XS Ineff= 2 , 0
         4917.87 1183.74
Permanent Ineff=
       F       F
Bank Sta=4984.6,4999
XS Rating Curve= 0 ,0
Exp/Cntr=0.3,0.1

Type RM Length L Ch R = 1 ,44000   ,500,500,500
BEGIN DESCRIPTION:
OATMAN CREEK 87.0
END DESCRIPTION:
XS GIS Cut Line= 3
      2812705.66     10212253.13      2813230.62     10212004.88
      2813455.67     10211503.14
#Sta/Elev= 30
  4419.3 1189.65  4450.7 1186.12  4473.5 1185.21  4485.7  1186.2  4575.6 1181.75
  4621.1 1180.61  4651.6 1178.07  4673.8 1174.94  4695.9 1177.22  4712.1 1177.68
  4785.9    1178  4831.4 1176.02  4945.2 1175.56  4973.5 1166.74  4983.5  1167.1
  4990.7 1166.21  4996.6 1163.96  4997.1 1163.46    5011 1163.96  5012.9 1166.23
  5034.8 1166.52  5056.7 1169.26  5077.2 1169.91  5111.5 1169.05  5125.2 1170.18
  5142.9 1176.17  5182.8 1177.08  5269.7 1177.61  5407.5 1185.83  5549.9 1196.16
#Mann= 5 ,-1 , 0
  4419.3     .05       0  4996.6     .03       0    5011     .05       0
  5077.2     .12       0  5182.8     .05       0
Bank Sta=4996.6,5011
XS Rating Curve= 0 ,0
Exp/Cntr=0.3,0.1

Type RM Length L Ch R = 1 ,43500   ,500,500,500
BEGIN DESCRIPTION:
OATMAN CREEK 86.0
END DESCRIPTION:
XS GIS Cut Line= 3
      2812855.66     10212753.13      2813688.85     10212100.11
      2814105.64     10211903.13
#Sta/Elev= 30
  3941.4 1201.06  4112.3 1195.32  4532.7 1171.69  4803.9 1172.22  4839.1 1173.25
  4845.5 1174.81  4868.1 1172.85  4909.7 1173.49  4967.5    1164    4982  1163.4
  4987.6 1158.35  4988.1 1157.85  5002.1 1158.35  5008.9 1162.43  5018.6 1165.31
  5042.4 1169.45  5062.9 1173.97  5099.9 1174.64  5129.2 1167.13  5139.9 1167.09
  5145.5 1169.52  5162.4  1165.7  5168.2 1167.44  5173.8 1165.83  5184.5 1170.23
    5191 1176.13  5196.5 1174.67    5316 1180.28  5333.1 1180.22    5461 1191.07
#Mann= 5 ,-1 , 0
  3941.4     .05       0  4987.6     .05       0  5002.1     .05       0
  5042.4     .12       0    5316     .05       0
Bank Sta=4987.6,5002.1
XS Rating Curve= 0 ,0
Exp/Cntr=0.3,0.1

Type RM Length L Ch R = 1 ,43000   ,500,500,500
BEGIN DESCRIPTION:
OATMAN CREEK 85.0
END DESCRIPTION:
XS GIS Cut Line= 3
      2813055.65     10212753.12      2813926.76     10212536.69
      2814305.71     10212053.07
#Sta/Elev= 30
  4102.4 1195.63  4195.2 1192.02  4349.7 1182.04  4504.3 1174.19  4663.2 1168.97
  4699.4 1165.01  4740.7 1165.64  4787.2 1168.19  4906.1 1166.72  4957.7 1168.74
  4978.3 1162.15  4986.5 1156.38    4987 1155.88  5001.4 1156.38  5004.4 1157.12
  5008.6 1159.22  5023.1 1162.27  5037.5 1162.64  5043.9 1164.03  5093.6 1168.03
  5116.2    1169  5122.5 1168.14  5201.2  1173.1    5222  1173.4  5240.4 1174.69
  5342.7 1180.87  5486.9 1192.86  5542.9 1199.33  5586.3 1202.21  5614.4  1206.3
#Mann= 7 ,-1 , 0
  4102.4     .05       0  4986.5     .03       0  5001.4     .05       0
  5004.4     .12       0    5222     .05       0  5240.4     .12       0
  5342.7     .05       0
Bank Sta=4986.5,5001.4
XS Rating Curve= 0 ,0
Exp/Cntr=0.3,0.1

Type RM Length L Ch R = 1 ,42500   ,500,500,500
BEGIN DESCRIPTION:
OATMAN CREEK 84.0
END DESCRIPTION:
XS GIS Cut Line= 3
      2813155.71     10212853.11      2814163.81     10212929.67
      2814555.69     10212453.11
#Sta/Elev= 30
    3989 1190.42  4149.4 1183.39  4269.8 1181.26  4448.2 1170.06  4640.8 1162.26
  4851.9 1164.57  4951.7 1162.27  4978.1 1159.03  4983.1 1157.76  4990.9 1153.48
  4991.4 1152.98    5006 1153.48  5012.9 1155.14  5020.8 1153.64  5027.2 1159.38
  5034.4 1157.48  5041.6    1154  5048.1 1160.36  5055.9 1158.41  5062.4 1163.42
  5070.3 1160.64  5084.6 1165.15  5212.3 1168.31    5297 1172.91  5335.9 1176.64
  5403.9 1185.87  5410.4 1185.45  5482.1 1192.38  5609.8 1200.49    5617 1201.74
#Mann= 4 ,-1 , 0
    3989     .05       0  4990.9     .05       0    5006     .05       0
  5335.9     .12       0
Bank Sta=4990.9,5006
XS Rating Curve= 0 ,0
Exp/Cntr=0.3,0.1

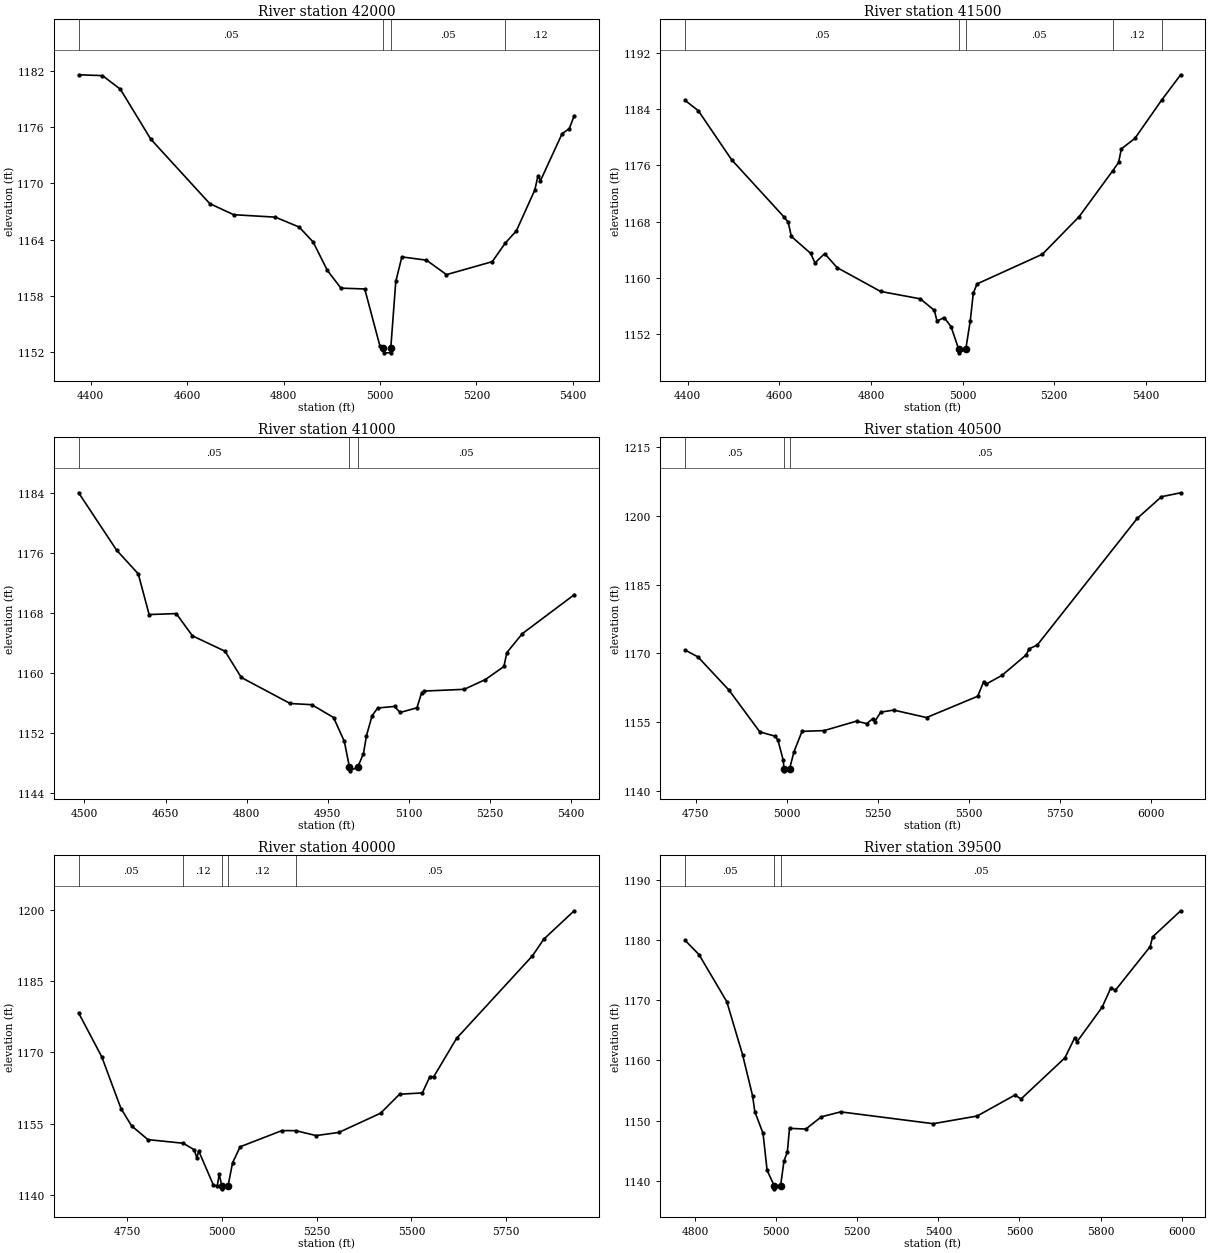
Type RM Length L Ch R = 1 ,42000   ,500,500,500
BEGIN DESCRIPTION:
OATMAN CREEK 83.0
END DESCRIPTION:
XS GIS Cut Line= 3
      2813405.65     10212953.09      2813911.14     10213320.83
      2814305.65     10213403.11
#Sta/Elev= 30
  4374.9 1181.58  4424.4 1181.49  4461.5 1180.04  4524.5 1174.72    4647 1167.84
  4696.5 1166.66    4783  1166.4  4832.5 1165.34  4861.4 1163.75  4890.8 1160.73
  4919.1 1158.83  4968.5 1158.74  4999.7 1152.71  5007.3 1152.43  5007.8 1151.93
    5022 1151.93  5022.5 1152.43  5032.9 1159.54  5045.5 1162.16  5096.6 1161.81
  5138.1 1160.27    5233 1161.65  5260.3 1163.65  5283.1 1164.94  5321.3 1169.29
    5328 1170.82  5333.1 1170.29    5378  1175.3  5392.8 1175.83    5403  1177.2
#Mann= 4 ,-1 , 0
  4374.9     .05       0  5007.3     .05       0  5022.5     .05       0
  5260.3     .12       0
Bank Sta=5007.3,5022.5
XS Rating Curve= 0 ,0
Exp/Cntr=0.3,0.1

Type RM Length L Ch R = 1 ,41500   ,500,500,500
BEGIN DESCRIPTION:
OATMAN CREEK 82.0
END DESCRIPTION:
XS GIS Cut Line= 3
      2813205.68     10213453.11      2813716.42     10213778.71
      2814105.72     10214053.14
#Sta/Elev= 30
  4394.3 1185.24  4423.1 1183.78  4495.9 1176.81    4611 1168.63  4619.6  1167.9
  4626.2 1165.92  4668.5 1163.51  4677.8 1162.15    4699 1163.47  4726.4 1161.48
  4821.2  1158.1    4908 1157.05  4938.5 1155.41  4944.4 1153.88  4959.7 1154.39
  4974.9 1153.12  4991.8 1149.88  4992.3 1149.38  5007.1 1149.88  5016.9  1153.9
  5023.6 1157.86  5031.7 1159.17  5174.5 1163.39  5254.6 1168.72  5327.7 1175.22
  5340.8 1176.42  5346.9 1178.36  5376.5 1179.85  5434.7 1185.27  5476.3 1188.88
#Mann= 5 ,-1 , 0
  4394.3     .05       0  4991.8     .03       0  5007.1     .05       0
  5327.7     .12       0  5434.7     .05       0
Bank Sta=4991.8,5007.1
XS Rating Curve= 0 ,0
Exp/Cntr=0.3,0.1

Type RM Length L Ch R = 1 ,41000   ,500,500,500
BEGIN DESCRIPTION:
OATMAN CREEK 81.0
END DESCRIPTION:
XS GIS Cut Line= 3
      2812905.73     10214053.12       2813414.8     10214093.85
      2813805.72     10214203.12
#Sta/Elev= 30
  4489.3 1183.98  4559.5 1176.33  4599.6 1173.17  4619.7 1167.74  4669.8 1167.87
  4699.9  1164.9  4760.1 1162.85  4790.2 1159.35  4880.5 1155.88  4920.6 1155.72
  4960.8 1154.01  4980.8 1150.82  4990.2  1147.4  4990.7  1146.9  5005.6  1147.4
  5016.2 1149.21  5021.7 1151.58  5032.1 1154.25  5042.5 1155.28  5073.6 1155.49
    5084 1154.68  5115.1 1155.31  5123.8 1157.34    5129 1157.54  5202.5 1157.77
  5241.8 1159.08    5276 1160.82  5281.3 1162.66  5310.1  1165.2  5405.9 1170.38
#Mann= 3 ,-1 , 0
  4489.3     .05       0  4990.2     .05       0  5005.6     .05       0
Bank Sta=4990.2,5005.6
XS Rating Curve= 0 ,0
Exp/Cntr=0.3,0.1

Type RM Length L Ch R = 1 ,40500   ,500,500,500
BEGIN DESCRIPTION:
OATMAN CREEK 80.0
END DESCRIPTION:
XS GIS Cut Line= 3
      2812955.68     10214303.11      2813145.22     10214508.52
      2814105.66      10215003.1
#Sta/Elev= 30
  4720.5 1170.72  4755.9 1169.22    4841 1161.98  4925.5 1152.89    4968 1151.94
  4975.4 1151.04  4989.6 1146.79    4992  1144.9  4992.5  1144.4  5007.4  1144.9
  5019.2 1148.54  5041.3    1153  5101.8 1153.17  5190.9 1155.23  5218.7 1154.69
  5235.2 1155.74  5240.9 1155.14  5257.4 1157.19    5293 1157.64    5383 1156.01
  5523.4 1160.65    5540 1163.86  5545.6 1163.26    5590  1165.2  5656.5 1169.67
  5664.2 1170.97  5686.7  1171.8  5961.2 1199.41  6027.7 1204.13  6080.3 1204.99
#Mann= 3 ,-1 , 0
  4720.5     .05       0    4992     .05       0  5007.4     .05       0
Bank Sta=4992,5007.4
XS Rating Curve= 0 ,0
Exp/Cntr=0.3,0.1

Type RM Length L Ch R = 1 ,40000   ,500,500,500
BEGIN DESCRIPTION:
OATMAN CREEK 79.0
END DESCRIPTION:
XS GIS Cut Line= 3
      2812705.68     10214853.11      2813077.22     10214919.34
      2814005.71     10214953.11
#Sta/Elev= 30
  4622.6 1178.29  4683.6 1169.08  4734.3  1158.2  4762.4 1154.55  4805.4 1151.68
  4898.3 1150.92  4927.3 1149.55  4934.2 1147.87  4939.3 1149.29  4978.1 1142.09
  4988.1 1141.99  4993.2 1144.36  5000.7 1141.84  5001.2 1141.34  5016.2 1141.84
  5028.5 1146.82  5048.5 1150.18  5158.6 1153.58  5195.2 1153.56  5248.6 1152.53
  5308.7 1153.19  5418.7 1157.23  5468.8 1161.22  5528.8 1161.49  5548.8 1164.94
  5558.8 1164.89  5618.9 1172.94    5819 1190.29    5849  1193.8  5929.1 1199.76
#Mann= 5 ,-1 , 0
  4622.6     .05       0  4898.3     .12       0  5000.7     .07       0
  5016.2     .12       0  5195.2     .05       0
Bank Sta=5000.7,5016.2
XS Rating Curve= 0 ,0
Exp/Cntr=0.3,0.1

Type RM Length L Ch R = 1 ,39500   ,500,500,500
BEGIN DESCRIPTION:
OATMAN CREEK 78.0
END DESCRIPTION:
XS GIS Cut Line= 3
      2812605.66     10215203.11       2812827.7     10215236.95
      2813755.67     10215603.11
#Sta/Elev= 30
  4775.4  1179.9  4809.7 1177.54  4878.3 1169.72    4917 1160.96  4941.8 1154.12
  4947.4 1151.47  4967.6 1147.88  4977.7 1141.73  4995.4 1139.17  4995.9 1138.67
  5010.9 1139.17  5019.3 1143.29  5027.6 1144.79  5032.9 1148.71  5073.1 1148.59
  5111.4 1150.62  5159.1 1151.44  5387.4 1149.48  5495.6 1150.75  5589.1 1154.24
  5603.9 1153.58  5712.1  1160.4  5736.5 1163.76  5741.9 1163.07  5804.1 1168.82
  5825.7 1172.06  5836.4  1171.6  5922.4 1178.86  5928.6 1180.49  5997.6 1184.81
#Mann= 3 ,-1 , 0
  4775.4     .05       0  4995.4     .05       0  5010.9     .05       0
Bank Sta=4995.4,5010.9
XS Rating Curve= 0 ,0
Exp/Cntr=0.3,0.1

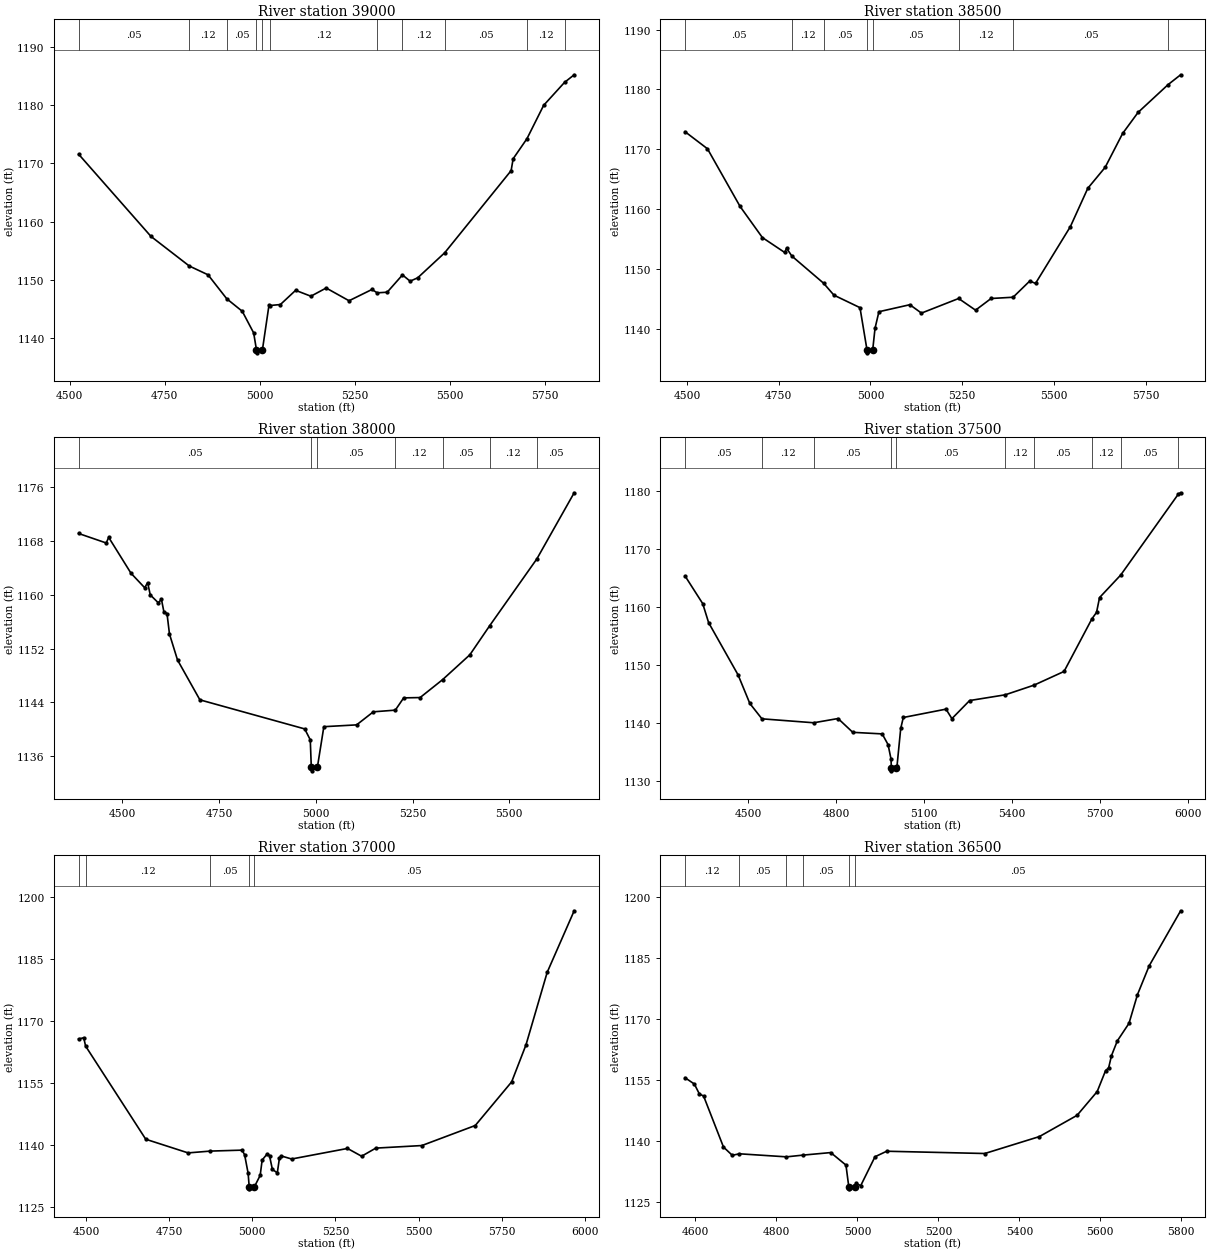
Type RM Length L Ch R = 1 ,39000   ,500,500,500
BEGIN DESCRIPTION:
OATMAN CREEK 77.0
END DESCRIPTION:
XS GIS Cut Line= 3
       2812455.7     10215653.11      2812931.03     10215678.37
      2813755.65     10215753.11
#Sta/Elev= 30
    4524 1171.58  4714.3 1157.46  4815.2 1152.37  4864.5 1150.86  4913.8 1146.74
  4954.6 1144.59  4984.6 1140.87    4992 1137.95  4992.5 1137.45  5007.6 1137.95
  5024.8 1145.59  5027.3 1145.58  5054.9 1145.75    5095 1148.19  5135.2 1147.18
  5175.4 1148.59  5235.6  1146.4  5295.9 1148.34  5309.6 1147.76    5336 1147.87
  5376.2 1150.84  5396.3 1149.76  5416.4 1150.35  5487.4 1154.65  5662.1 1168.76
  5667.4  1170.8  5703.8 1174.25  5747.7 1179.98  5802.6 1183.92    5828 1185.23
#Mann= 11 ,-1 , 0
    4524     .05       0  4815.2     .12       0  4913.8     .05       0
    4992     .05       0  5007.6     .05       0  5027.3     .12       0
  5309.6     .05       0  5376.2     .12       0  5487.4     .05       0
  5703.8     .12       0  5802.6     .05       0
Bank Sta=4992,5007.6
XS Rating Curve= 0 ,0
Exp/Cntr=0.3,0.1

Type RM Length L Ch R = 1 ,38500   ,500,500,500
BEGIN DESCRIPTION:
OATMAN CREEK 76.0
END DESCRIPTION:
XS GIS Cut Line= 3
      2812455.64     10216253.12      2812953.69     10216170.23
      2813755.68     10215903.11
#Sta/Elev= 30
  4495.1 1172.92    4556 1170.08  4644.8 1160.45  4705.7 1155.24  4766.5 1152.75
  4771.6 1153.47  4785.8 1152.16  4872.5 1147.61  4900.6 1145.62  4971.6 1143.53
  4990.7 1136.48  4991.2 1135.98  5006.3 1136.48  5012.6 1140.08  5023.2 1142.85
  5107.5 1144.02  5139.1 1142.62  5240.4 1145.06  5286.5 1143.11  5328.8 1145.06
  5388.8 1145.27  5434.2 1147.98  5449.9 1147.58  5544.8 1157.06  5592.3 1163.47
  5639.7 1166.98  5687.2 1172.63  5729.3 1176.15  5811.2  1180.8  5845.3 1182.44
#Mann= 8 ,-1 , 0
  4495.1     .05       0  4785.8     .12       0  4872.5     .05       0
  4990.7     .03       0  5006.3     .05       0  5240.4     .12       0
  5388.8     .05       0  5811.2     .12       0
Bank Sta=4990.7,5006.3
XS Rating Curve= 0 ,0
Exp/Cntr=0.3,0.1

Type RM Length L Ch R = 1 ,38000   ,500,500,500
BEGIN DESCRIPTION:
OATMAN CREEK 75.0
END DESCRIPTION:
XS GIS Cut Line= 3
      2812805.71     10216903.09       2813286.7     10216523.08
      2813705.71     10216003.08
#Sta/Elev= 30
    4387  1169.1  4458.3 1167.69  4464.7 1168.52  4522.4 1163.19  4557.7 1161.04
  4565.4  1161.8  4572.1 1159.98  4592.9  1158.8    4601 1159.32  4607.4 1157.45
  4615.4 1157.21  4621.8 1154.16  4642.6  1150.3  4700.4 1144.38  4971.3 1140.06
  4985.7 1138.44  4988.4 1134.33  4988.9 1133.83    5004 1134.33  5020.8 1140.39
  5105.5 1140.66  5148.7  1142.6  5205.5 1142.85  5227.1 1144.67  5269.6 1144.72
  5327.5 1147.37  5398.1 1151.07  5449.5  1155.4  5571.4 1165.33  5667.8 1175.15
#Mann= 7 ,-1 , 0
    4387     .05       0  4988.4     .03       0    5004     .05       0
  5205.5     .12       0  5327.5     .05       0  5449.5     .12       0
  5571.4     .05       0
Bank Sta=4988.4,5004
XS Rating Curve= 0 ,0
Exp/Cntr=0.3,0.1

Type RM Length L Ch R = 1 ,37500   ,500,500,500
BEGIN DESCRIPTION:
OATMAN CREEK 74.0
END DESCRIPTION:
XS GIS Cut Line= 4
      2812905.69     10216903.11      2813618.48     10216852.24
      2813684.21     10216876.85      2813780.69      10215978.1
#Sta/Elev= 30
  4285.4 1165.31  4345.5 1160.55  4365.6 1157.27  4465.9 1148.27    4506 1143.34
  4547.2 1140.69  4723.7 1140.01  4806.7 1140.74  4856.8 1138.36  4957.1 1138.09
  4977.1 1136.24  4987.2 1133.74  4988.2 1132.22  4988.7 1131.72  5003.9 1132.22
  5007.7 1132.62  5020.2 1139.03    5029 1140.92  5174.5 1142.36  5194.6 1140.72
    5255 1143.84  5376.3 1144.83  5474.6  1146.5  5576.8 1148.86  5671.4  1157.9
  5687.5 1159.05  5697.8  1161.6  5769.8 1165.48  5966.5 1179.46  5974.1 1179.67
#Mann= 10 ,-1 , 0
  4285.4     .05       0  4547.2     .12       0  4723.7     .05       0
  4988.2     .03       0  5003.9     .05       0  5376.3     .12       0
  5474.6     .05       0  5671.4     .12       0  5769.8     .05       0
  5966.5     .12       0
Bank Sta=4988.2,5003.9
XS Rating Curve= 0 ,0
Exp/Cntr=0.3,0.1

Type RM Length L Ch R = 1 ,37000   ,500,500,500
BEGIN DESCRIPTION:
OATMAN CREEK 73.0
END DESCRIPTION:
XS GIS Cut Line= 3
      2812905.64      10217003.1      2813397.56     10217179.22
      2813905.69     10218003.13
#Sta/Elev= 30
  4477.5 1165.66  4492.9 1165.96  4498.4 1163.94  4679.4 1141.36  4806.8 1138.05
  4873.8 1138.49  4969.2 1138.72  4976.8 1137.58  4987.4 1133.07  4990.5 1129.84
    4991 1129.34  5006.2 1129.84  5023.6 1132.61  5029.5 1136.32  5044.9 1137.83
  5051.6 1137.39  5060.3 1134.03  5075.1 1133.22  5081.5 1136.79  5087.4  1137.3
  5118.2 1136.57  5286.2 1139.13  5328.7 1137.24  5371.3 1139.21  5509.8 1139.83
  5670.5 1144.69    5780 1155.27  5823.1 1164.24  5886.9 1181.83    5968 1196.73
#Mann= 5 ,-1 , 0
  4477.5     .05       0  4498.4     .12       0  4873.8     .05       0
  4990.5     .05       0  5006.2     .05       0
Bank Sta=4990.5,5006.2
XS Rating Curve= 0 ,0
Exp/Cntr=0.3,0.1

Type RM Length L Ch R = 1 ,36500   ,500,500,500
BEGIN DESCRIPTION:
OATMAN CREEK 72.0
END DESCRIPTION:
XS GIS Cut Line= 3
      2812805.69     10217403.11       2813177.1     10217610.93
      2813805.65     10218103.08
#Sta/Elev= 30
  4574.4 1155.56  4597.3 1154.02  4609.8 1151.55    4620 1151.09  4669.2 1138.52
  4690.9 1136.49  4708.4 1136.86  4824.8 1136.11  4866.1 1136.54  4934.1 1137.16
  4971.7 1134.08  4978.7 1128.74  4979.2 1128.24  4995.1 1128.74  4997.1  1129.6
  5008.1 1129.01  5043.4 1136.13  5072.3 1137.49  5314.6 1136.93  5449.3 1141.09
  5542.5 1146.32  5592.2 1152.17    5613 1157.34  5620.5 1158.02  5627.5    1161
  5641.9 1164.63  5670.8 1168.96  5691.7 1176.02  5720.6  1183.1  5798.3 1196.64
#Mann= 6 ,-1 , 0
  4574.4     .12       0  4708.4     .05       0  4824.8     .12       0
  4866.1     .05       0  4978.7     .05       0  4995.1     .05       0
Bank Sta=4978.7,4995.1
XS Rating Curve= 0 ,0
Exp/Cntr=0.3,0.1

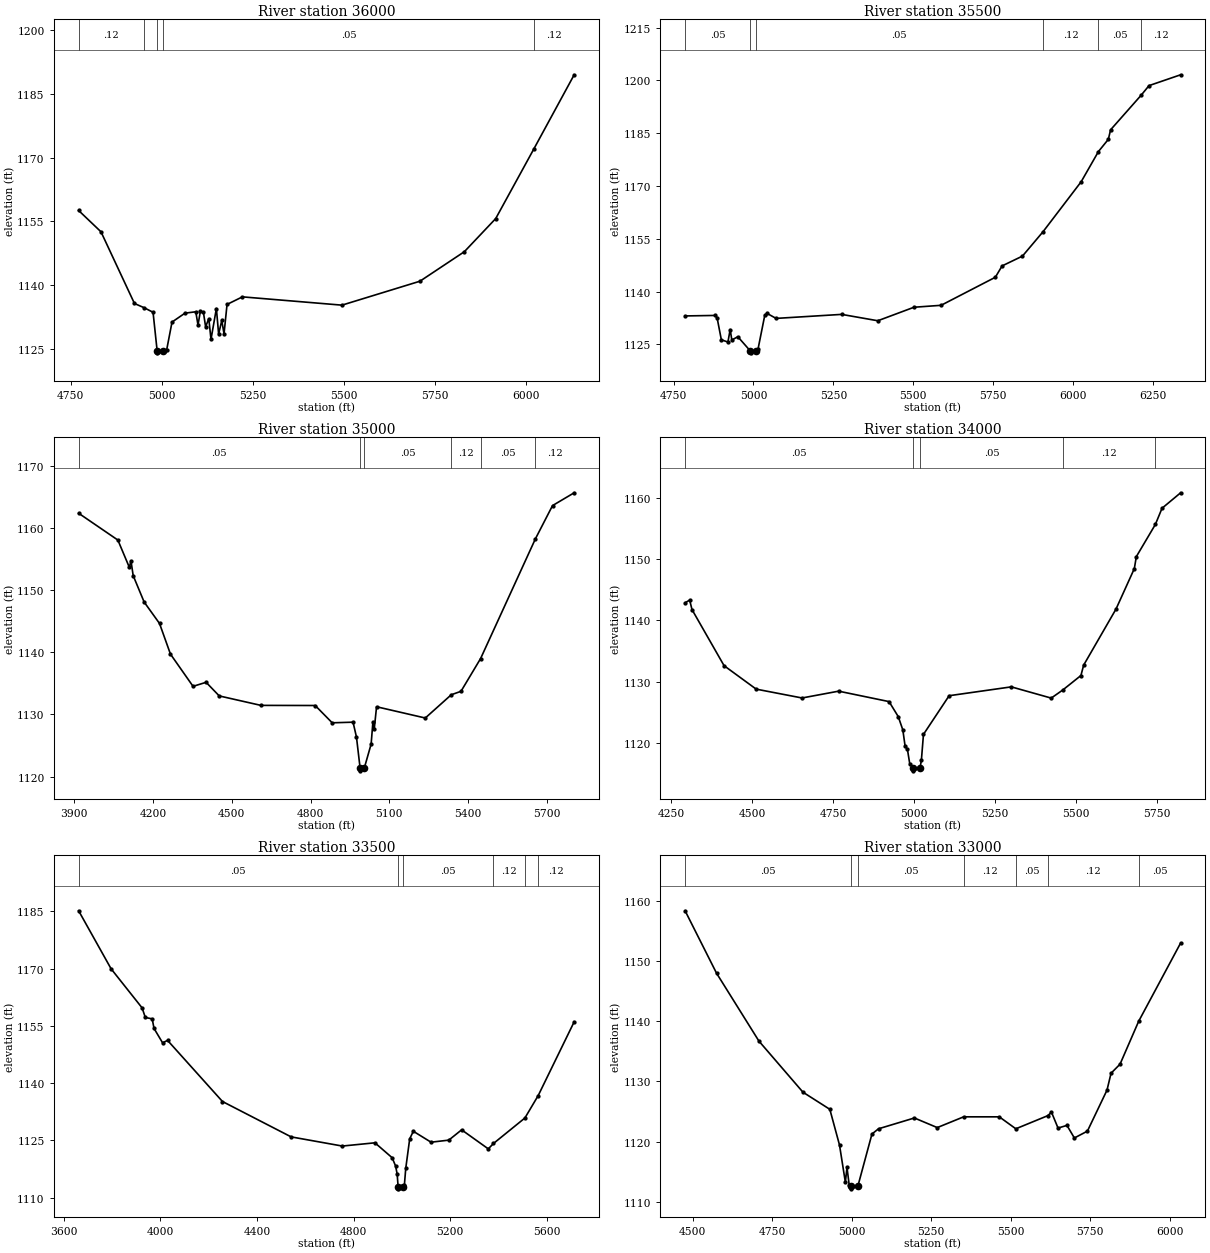
Type RM Length L Ch R = 1 ,36000   ,500,500,500
BEGIN DESCRIPTION:
OATMAN CREEK 71.0
END DESCRIPTION:
XS GIS Cut Line= 3
      2812755.68     10217403.09      2812803.29     10217626.06
      2813455.69     10218553.12
#Sta/Elev= 30
    4772 1157.57  4833.4 1152.56  4925.4 1135.69  4952.1 1134.69  4976.5 1133.62
  4987.7 1124.58  4988.2 1124.08  5004.1 1124.58  5013.8 1124.73  5028.6 1131.32
  5064.3 1133.42  5093.9 1133.74    5100 1130.62  5106.4 1133.82  5114.8 1133.65
  5120.9 1130.21  5129.6 1132.12  5135.7 1127.26  5150.5 1134.51  5156.7 1128.49
  5165.3  1131.7  5171.5 1128.55  5179.8 1135.47    5222 1137.25  5495.5  1135.3
  5709.8 1140.93  5831.8 1147.87    5918 1155.67  6023.3 1172.13  6133.6  1189.5
#Mann= 5 ,-1 , 0
    4772     .12       0  4952.1     .05       0  4987.7     .05       0
  5004.1     .05       0  6023.3     .12       0
Bank Sta=4987.7,5004.1
XS Rating Curve= 0 ,0
Exp/Cntr=0.3,0.1

Type RM Length L Ch R = 1 ,35500   ,500,500,500
BEGIN DESCRIPTION:
OATMAN CREEK 70.0
END DESCRIPTION:
XS GIS Cut Line= 3
       2812405.7     10217653.16      2812458.05     10217860.45
      2813405.65     10218803.08
#Sta/Elev= 30
  4786.2 1133.07    4879 1133.21  4886.2  1132.6  4899.6 1126.29  4920.2 1125.65
  4927.2  1129.2  4932.4 1126.23  4951.2 1127.16  4990.6 1123.08  4991.1 1122.58
    5007 1123.08  5014.3 1123.61  5035.6 1133.31  5042.6 1133.79  5070.9 1132.37
    5276 1133.51  5389.1  1131.7  5502.3 1135.54  5587.1 1136.09  5756.8 1144.06
    5778 1147.29  5841.7 1150.08  5906.1 1157.01  6025.5 1171.23  6079.5 1179.81
  6110.4 1183.27  6117.4 1185.97  6212.7 1195.77  6237.7 1198.54  6336.6 1201.62
#Mann= 6 ,-1 , 0
  4786.2     .05       0  4990.6     .05       0    5007     .05       0
  5906.1     .12       0  6079.5     .05       0  6212.7     .12       0
Bank Sta=4990.6,5007
XS Rating Curve= 0 ,0
Exp/Cntr=0.3,0.1

Type RM Length L Ch R = 1 ,35000   ,1000,1000,1000
BEGIN DESCRIPTION:
OATMAN CREEK 69.0
END DESCRIPTION:
XS GIS Cut Line= 3
      2812705.71     10217203.08       2812061.3     10218073.24
      2812255.68     10218853.09
#Sta/Elev= 30
  3917.2 1162.33  4066.6 1158.02  4110.3 1153.63  4116.5 1154.68  4124.9  1152.3
  4166.6 1148.06  4225.1 1144.62  4266.8 1139.69  4352.8 1134.51  4402.5 1135.16
  4452.5 1132.97  4611.2 1131.45  4817.8 1131.43  4882.5 1128.65  4961.9 1128.75
  4974.9 1126.36  4988.6 1121.43  4989.1 1120.93  5005.1 1121.43  5030.8 1125.24
  5037.4 1128.75  5042.5 1127.61  5051.4 1131.23  5236.9 1129.42  5335.9 1133.16
  5372.8 1133.71  5447.5 1138.98  5655.9  1158.2  5721.3 1163.56  5803.7 1165.62
#Mann= 6 ,-1 , 0
  3917.2     .05       0  4988.6     .03       0  5005.1     .05       0
  5335.9     .12       0  5447.5     .05       0  5655.9     .12       0
Bank Sta=4988.6,5005.1
XS Rating Curve= 0 ,0
Exp/Cntr=0.3,0.1

Type RM Length L Ch R = 1 ,34000   ,500,500,500
BEGIN DESCRIPTION:
OATMAN CREEK 67.0
END DESCRIPTION:
XS GIS Cut Line= 3
      2811155.65     10217603.08      2811664.28     10218092.85
      2812155.71     10218753.15
#Sta/Elev= 30
  4293.9 1142.87    4308 1143.31  4315.2 1141.76  4414.2 1132.62  4513.3  1128.8
  4654.8 1127.36  4767.7 1128.47  4923.3 1126.77  4951.6 1124.33  4965.8 1122.16
    4973 1119.46  4979.9 1119.02  4987.1 1116.66  4998.2 1115.99  4998.7 1115.49
  5019.1 1115.99  5023.2  1117.3  5029.5 1121.43  5108.7 1127.73  5300.6 1129.17
  5423.7 1127.34  5459.4 1128.66  5515.4 1131.02  5523.8 1132.71  5623.6 1141.84
  5680.2 1148.44  5686.4 1150.39  5745.1 1155.63  5765.7 1158.27  5823.1 1160.79
#Mann= 5 ,-1 , 0
  4293.9     .05       0  4998.2     .05       0  5019.1     .05       0
  5459.4     .12       0  5745.1     .05       0
Bank Sta=4998.2,5019.1
XS Rating Curve= 0 ,0
Exp/Cntr=0.3,0.1

Type RM Length L Ch R = 1 ,33500   ,500,500,500
BEGIN DESCRIPTION:
OATMAN CREEK 66.0
END DESCRIPTION:
XS GIS Cut Line= 3
       2810355.7     10217603.13       2811373.6     10218472.15
      2812005.69     10218803.12
#Sta/Elev= 30
  3661.6 1185.14  3796.1 1169.93  3924.5 1159.69  3937.7 1157.19  3966.2 1156.82
  3973.9  1154.3  4009.1 1150.56  4029.9 1151.18  4257.2 1135.17  4541.6  1125.9
  4753.4  1123.5  4888.5 1124.35  4959.8 1120.44  4974.1 1118.27  4980.7  1116.1
  4984.5 1112.79    4985 1112.29  5005.4 1112.79  5010.4 1113.24  5016.1 1117.66
  5032.5  1125.4  5047.5 1127.37  5120.8 1124.51  5194.3 1125.05  5247.5 1127.75
  5357.9 1122.76  5379.3 1124.17  5509.5 1130.85  5564.6 1136.73  5713.5 1156.05
#Mann= 6 ,-1 , 0
  3661.6     .05       0  4984.5     .05       0  5005.4     .05       0
  5379.3     .12       0  5509.5     .05       0  5564.6     .12       0
Bank Sta=4984.5,5005.4
XS Rating Curve= 0 ,0
Exp/Cntr=0.3,0.1

Type RM Length L Ch R = 1 ,33000   ,1000,1000,1000
BEGIN DESCRIPTION:
OATMAN CREEK 65.0
END DESCRIPTION:
XS GIS Cut Line= 3
      2810405.64     10218753.12      2810923.68     10218675.64
      2811931.27     10218907.84
#Sta/Elev= 30
  4476.2  1158.4    4575 1148.02  4708.3 1136.72  4846.7 1128.22  4931.2 1125.37
  4961.6 1119.43    4980 1113.25  4985.1  1115.7  4991.9 1112.85  4998.5 1112.64
    4999 1112.14  5019.6 1112.64  5063.6 1121.26  5084.2 1122.13    5197 1123.93
  5268.9 1122.33  5351.9 1124.12  5463.9 1124.12  5515.9 1122.13  5616.2 1124.31
    5628 1124.89  5648.6 1122.25  5676.6  1122.7  5699.9  1120.6  5740.9 1121.74
  5802.5 1128.56  5815.2 1131.37  5843.5 1132.88  5902.1 1140.02    6034 1153.04
#Mann= 7 ,-1 , 0
  4476.2     .05       0  4998.5     .05       0  5019.6     .05       0
  5351.9     .12       0  5515.9     .05       0  5616.2     .12       0
  5902.1     .05       0
Bank Sta=4998.5,5019.6
XS Rating Curve= 0 ,0
Exp/Cntr=0.3,0.1

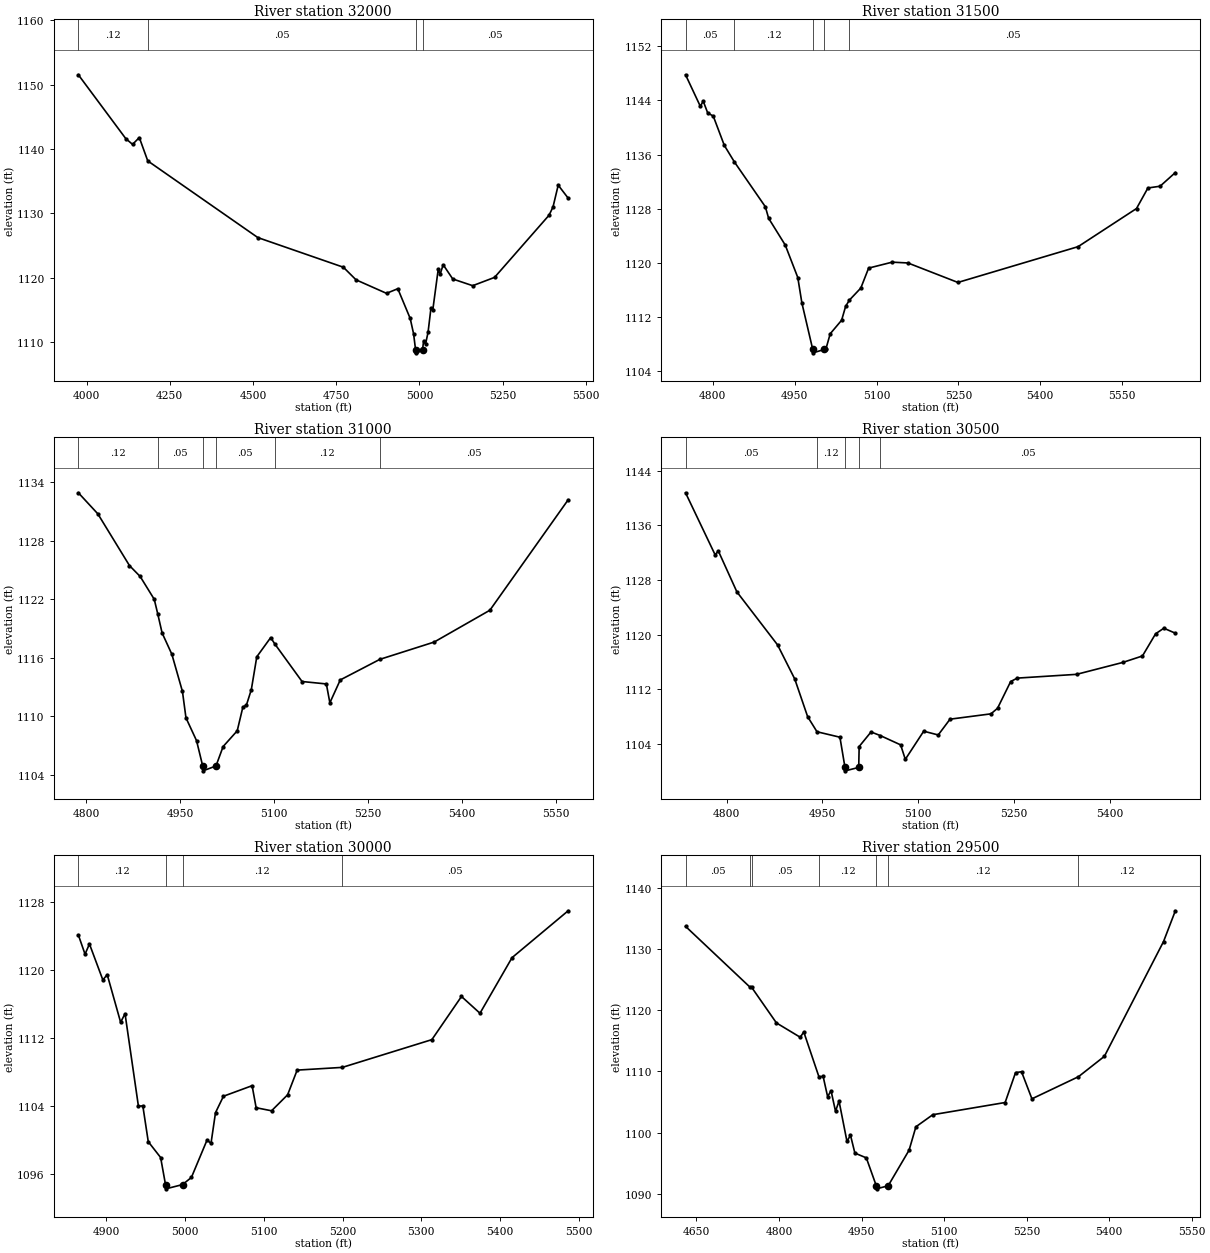
Type RM Length L Ch R = 1 ,32000   ,500,500,500
BEGIN DESCRIPTION:
OATMAN CREEK 63.0
END DESCRIPTION:
XS GIS Cut Line= 3
      2810305.67     10219453.11      2811312.92     10219265.93
      2811705.67     10219053.12
#Sta/Elev= 30
  3975.5 1151.54  4117.9 1141.62  4138.3 1140.72  4158.6 1141.78    4184 1138.15
  4514.6 1126.23  4771.5 1121.62  4809.6 1119.66  4901.1 1117.56    4935 1118.28
  4972.3 1113.65  4982.5 1111.25  4988.3 1108.81  4988.8 1108.31  5009.4 1108.81
  5012.6 1110.21  5018.3 1109.66  5025.9 1111.51  5034.5 1115.24  5040.2 1115.01
  5056.4 1121.29    5062 1120.54  5071.4    1122  5100.1 1119.79    5160 1118.75
  5225.6 1120.04  5389.2  1129.7  5401.2 1130.99  5416.8 1134.38  5446.7 1132.36
#Mann= 4 ,-1 , 0
  3975.5     .12       0    4184     .05       0  4988.3     .05       0
  5009.4     .05       0
Bank Sta=4988.3,5009.4
XS Rating Curve= 0 ,0
Exp/Cntr=0.3,0.1

Type RM Length L Ch R = 1 ,31500   ,500,500,500
BEGIN DESCRIPTION:
OATMAN CREEK 62.0
END DESCRIPTION:
XS GIS Cut Line= 3
      2811405.68     10219903.13      2811448.72     10219656.86
      2811855.68     10219153.11
#Sta/Elev= 30
    4750 1147.79  4777.2 1143.11  4782.3 1143.91  4790.6 1142.15  4800.8 1141.68
  4821.1 1137.34  4839.6 1134.89  4896.2 1128.28  4902.3 1126.56  4932.7 1122.61
  4955.7 1117.81  4963.2 1114.05  4983.1 1107.17  4983.6 1106.67  5004.3 1107.17
  5007.2 1107.23  5015.1 1109.49    5036 1111.49  5043.4 1113.55  5050.4 1114.48
  5071.2 1116.25  5085.5  1119.2  5128.7 1120.08  5157.5 1119.96  5249.1 1117.08
  5469.3 1122.37  5576.4 1128.01  5597.3 1131.05  5619.6 1131.31  5647.6 1133.33
#Mann= 5 ,-1 , 0
    4750     .05       0  4839.6     .12       0  4983.1     .07       0
  5004.3     .12       0  5050.4     .05       0
Bank Sta=4983.1,5004.3
XS Rating Curve= 0 ,0
Exp/Cntr=0.3,0.1

Type RM Length L Ch R = 1 ,31000   ,500,500,500
BEGIN DESCRIPTION:
OATMAN CREEK 61.0
END DESCRIPTION:
XS GIS Cut Line= 3
      2811705.66     10219953.12      2811896.21     10219859.97
      2812155.68     10219353.12
#Sta/Elev= 30
  4787.9 1132.89  4818.9 1130.74  4869.5 1125.43  4886.5 1124.32    4909 1121.98
  4914.5 1120.51  4921.5 1118.54  4937.1 1116.35    4954 1112.54  4959.6 1109.84
  4976.5  1107.5  4986.3 1104.91  4986.8 1104.41  5007.5 1104.91  5018.9  1106.9
  5041.4 1108.51  5050.4 1110.94    5056 1111.13  5063.9 1112.73  5072.6 1116.09
  5094.8 1118.06  5101.2 1117.42  5144.8 1113.56  5183.6 1113.31  5189.2 1111.38
  5205.8 1113.72    5269 1115.83  5355.6  1117.6  5444.5 1120.86  5569.4 1132.17
#Mann= 6 ,-1 , 0
  4787.9     .12       0  4914.5     .05       0  4986.3     .05       0
  5007.5     .05       0  5101.2     .12       0    5269     .05       0
Bank Sta=4986.3,5007.5
XS Rating Curve= 0 ,0
Exp/Cntr=0.3,0.1

Type RM Length L Ch R = 1 ,30500   ,500,500,500
BEGIN DESCRIPTION:
OATMAN CREEK 60.0
END DESCRIPTION:
XS GIS Cut Line= 3
      2812305.69      10220353.1      2812333.55     10220090.48
      2812455.68     10219603.14
#Sta/Elev= 30
  4735.9 1140.77  4782.2 1131.69  4787.2 1132.26  4816.3 1126.26  4879.9 1118.51
  4906.8 1113.52    4927    1108  4941.6  1105.8  4977.5    1105  4985.4 1100.58
  4985.9 1100.08  5006.9 1100.58  5007.6 1103.64  5026.2 1105.77  5040.7 1105.24
  5072.5 1103.88  5079.8 1101.76  5108.6 1105.88  5131.3 1105.33  5149.8 1107.64
  5213.8 1108.42  5224.1 1109.23  5244.7 1113.15    5255 1113.65  5347.8  1114.2
    5420 1115.94  5450.9 1116.89  5471.5 1120.14  5484.4 1120.95  5502.4 1120.22
#Mann= 5 ,-1 , 0
  4735.9     .05       0  4941.6     .12       0  4985.4     .07       0
  5006.9     .12       0  5040.7     .05       0
Bank Sta=4985.4,5006.9
XS Rating Curve= 0 ,0
Exp/Cntr=0.3,0.1

Type RM Length L Ch R = 1 ,30000   ,500,500,500
BEGIN DESCRIPTION:
OATMAN CREEK 59.0
END DESCRIPTION:
XS GIS Cut Line= 3
      2812755.68     10220303.11      2812814.61      10220181.1
      2812905.69      10219703.1
#Sta/Elev= 30
  4864.5 1124.12    4873 1121.86  4878.6 1123.06  4895.6 1118.84  4901.2 1119.45
  4918.2 1113.86  4923.8 1114.87  4940.8    1104  4946.4 1104.04  4953.3 1099.83
    4969 1097.97  4975.2 1094.79  4975.7 1094.29  4996.8 1094.79  5008.1 1095.63
  5027.9 1100.01    5033 1099.64  5038.7 1103.24  5048.8 1105.17  5085.2 1106.41
  5090.3 1103.82  5109.9 1103.46  5130.3 1105.34  5142.4 1108.24  5199.8 1108.56
  5313.5 1111.82  5351.1 1116.89  5374.6 1114.92  5415.3 1121.45  5486.6 1126.96
#Mann= 4 ,-1 , 0
  4864.5     .12       0  4975.2     .07       0  4996.8     .12       0
  5199.8     .05       0
Bank Sta=4975.2,4996.8
XS Rating Curve= 0 ,0
Exp/Cntr=0.3,0.1

Type RM Length L Ch R = 1 ,29500   ,358,358,358
BEGIN DESCRIPTION:
OATMAN CREEK 58.0
END DESCRIPTION:
XS GIS Cut Line= 3
      2813067.37     10220376.74       2813297.3     10220086.98
       2813105.7     10219603.14
#Sta/Elev= 30
  4630.1 1133.67  4747.3 1123.75  4750.3 1123.72  4795.3 1117.92  4838.6 1115.58
    4845 1116.45  4872.5 1109.15  4880.2 1109.19  4888.3 1105.91  4894.6 1106.85
  4902.7 1103.51  4909.1 1105.17  4923.5  1098.6  4929.9 1099.61  4937.9 1096.69
  4958.7 1095.91  4976.8 1091.36  4977.3 1090.86  4998.4 1091.36  5036.4 1097.16
  5048.8 1100.98  5079.5 1102.95    5211 1104.94  5229.9 1109.81  5240.8 1109.96
  5259.7 1105.54  5344.3 1109.15  5391.4 1112.47  5498.9 1131.19  5520.4 1136.21
#Mann= 7 ,-1 , 0
  4630.1     .05       0  4747.3     .12       0  4750.3     .05       0
  4872.5     .12       0  4976.8     .05       0  4998.4     .12       0
  5344.3     .12       0
Bank Sta=4976.8,4998.4
XS Rating Curve= 0 ,0
Exp/Cntr=0.3,0.1