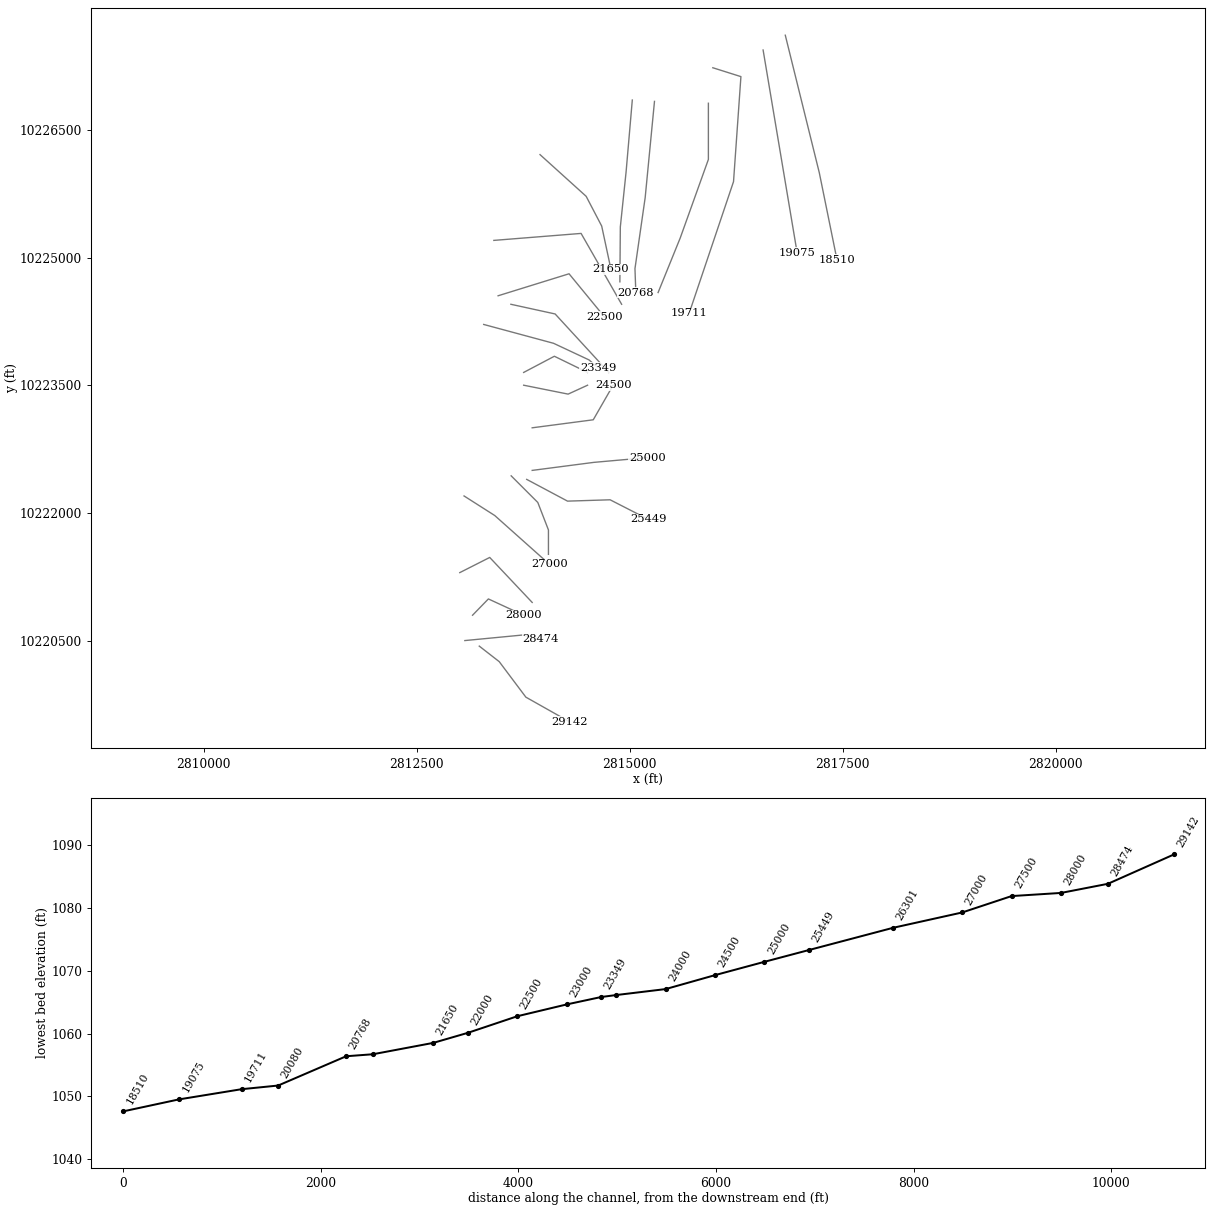
HEC-RAS study OATMAN CREEK.prj: OATMAN CREEK Base Level Engineering

--- OATMAN CREEK.g01 (geometry) --- (continued)

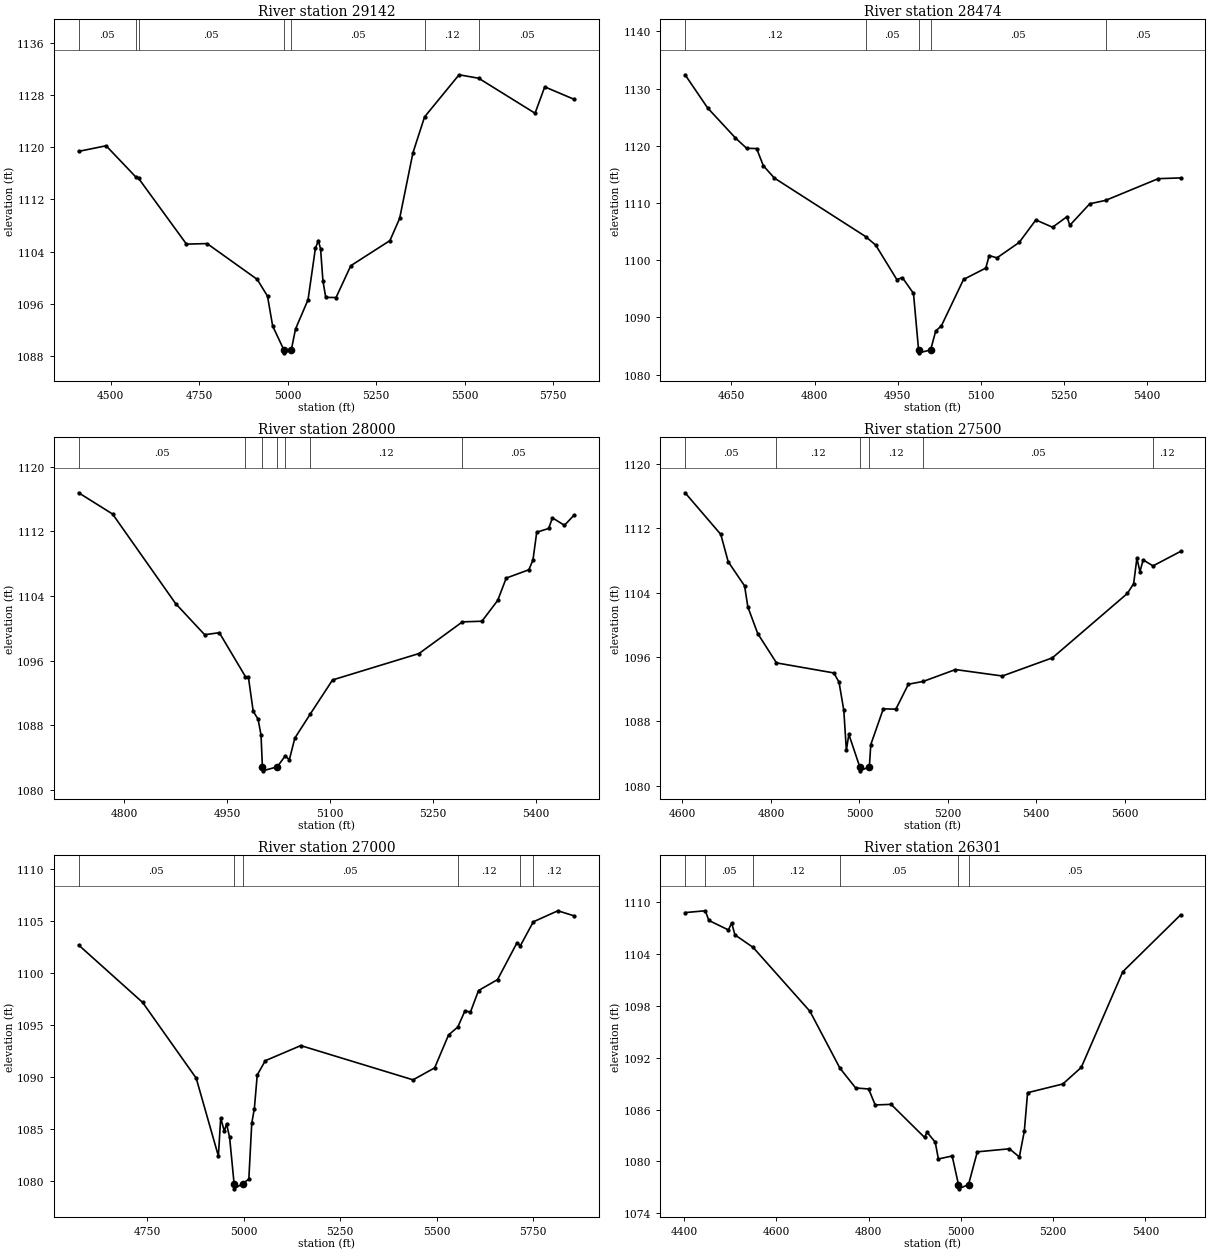
Type RM Length L Ch R = 1 ,29142   ,668,668,668
BEGIN DESCRIPTION:
Mapping XS 6a236cfd
END DESCRIPTION:
XS GIS Cut Line= 4
      2813234.38     10220440.36      2813468.77     10220258.06
      2813781.27     10219841.39      2814289.07     10219554.94
#Sta/Elev= 30
  4409.1 1119.34  4486.8  1120.2  4571.1  1115.4  4578.4 1115.22  4713.9 1105.14
  4772.2 1105.22  4913.9 1099.74    4943 1097.17  4957.6 1092.59  4988.9 1088.99
  4989.4 1088.49  5010.5 1088.99  5022.2 1092.14  5057.6 1096.62  5078.4  1104.5
  5086.8 1105.68    5093  1104.4  5099.7 1099.52  5107.6 1096.98  5136.8 1096.96
  5178.4 1101.83  5289.1 1105.68  5316.5 1109.07  5354.1 1119.12    5387 1124.62
  5484.5 1131.07  5539.9 1130.54  5699.3 1125.18  5726.7 1129.22  5809.9 1127.31
#Mann= 7 ,-1 , 0
  4409.1     .05       0  4571.1     .12       0  4578.4     .05       0
  4988.9     .03       0  5010.5     .05       0    5387     .12       0
  5539.9     .05       0
Bank Sta=4988.9,5010.5
XS Rating Curve= 0 ,0
Exp/Cntr=0.3,0.1

Type RM Length L Ch R = 1 ,28474   ,474,474,474
BEGIN DESCRIPTION:
Mapping XS 61fe45d2
END DESCRIPTION:
XS GIS Cut Line= 3
      2813065.08     10220505.45      2813742.21     10220570.56
      2813950.54     10220518.48
#Sta/Elev= 30
  4566.2 1132.43    4607 1126.62  4657.2 1121.38  4677.3 1119.58  4695.4 1119.53
  4707.5 1116.53  4727.5 1114.37  4892.2 1104.15  4910.4 1102.66  4948.6 1096.63
  4958.6 1096.98  4978.7 1094.21  4987.9 1084.32  4988.4 1083.82  5009.6 1084.32
  5018.9 1087.66  5028.9  1088.5  5069.1 1096.65  5109.3 1098.64  5115.4 1100.83
  5129.4 1100.42  5169.6 1103.12  5199.7 1107.05  5229.9 1105.78  5255.9 1107.62
    5261 1106.11  5297.1 1109.88  5325.6 1110.47  5420.8 1114.27  5461.2  1114.4
#Mann= 5 ,-1 , 0
  4566.2     .12       0  4892.2     .05       0  4987.9     .07       0
  5009.6     .05       0  5325.6     .05       0
Bank Sta=4987.9,5009.6
XS Rating Curve= 0 ,0
Exp/Cntr=0.3,0.1

Type RM Length L Ch R = 1 ,28000   ,500,500,500
BEGIN DESCRIPTION:
OATMAN CREEK 55.0
END DESCRIPTION:
XS GIS Cut Line= 3
      2813155.66     10220803.09      2813341.41     10220994.19
      2813755.67     10220803.12
#Sta/Elev= 30
  4733.5 1116.79    4783 1114.16  4874.9 1103.08  4917.3 1099.22  4938.7 1099.47
  4976.8 1094.03  4981.1 1093.97  4988.1 1089.74  4995.2 1088.77  4999.5 1086.81
  5001.5 1082.87    5002 1082.37  5023.2 1082.87  5034.8 1084.22  5040.8 1083.74
  5048.8 1086.42  5071.3  1089.4  5103.8 1093.62  5229.9 1096.89  5293.2 1100.81
  5321.7 1100.89  5344.7 1103.47  5357.1 1106.23  5390.1 1107.26  5396.1 1108.47
  5401.6 1111.91    5419 1112.37  5424.5 1113.69    5442 1112.76  5456.2 1114.04
#Mann= 7 ,-1 , 0
  4733.5     .05       0  4976.8     .12       0  5001.5     .07       0
  5023.2     .12       0  5034.8     .05       0  5071.3     .12       0
  5293.2     .05       0
Bank Sta=5001.5,5023.2
XS Rating Curve= 0 ,0
Exp/Cntr=0.3,0.1

Type RM Length L Ch R = 1 ,27500   ,500,500,500
BEGIN DESCRIPTION:
OATMAN CREEK 54.0
END DESCRIPTION:
XS GIS Cut Line= 3
       2813005.7     10221303.12      2813357.11     10221481.29
      2813855.67     10220953.13
#Sta/Elev= 30
    4606 1116.41  4686.7 1111.24  4703.4 1107.85  4740.5 1104.84  4747.9 1102.22
  4770.2 1098.92  4812.6 1095.28  4942.3 1094.03    4954 1092.89  4964.8 1089.38
  4970.6 1084.44  4976.2  1086.4  5000.8 1082.37  5001.3 1081.87  5022.6 1082.37
  5025.8 1085.13  5054.1 1089.57  5082.5 1089.53  5110.8 1092.63  5144.5 1092.98
  5217.2 1094.45  5323.2 1093.65  5436.5 1095.91    5606 1103.91  5620.1 1105.13
  5627.4 1108.28  5634.3 1106.62  5641.6 1108.07  5663.9 1107.33  5726.3 1109.13
#Mann= 6 ,-1 , 0
    4606     .05       0  4812.6     .12       0  5000.8     .07       0
  5022.6     .12       0  5144.5     .05       0  5663.9     .12       0
Bank Sta=5000.8,5022.6
XS Rating Curve= 0 ,0
Exp/Cntr=0.3,0.1

Type RM Length L Ch R = 1 ,27000   ,699,699,699
BEGIN DESCRIPTION:
OATMAN CREEK 53.0
END DESCRIPTION:
XS GIS Cut Line= 3
      2813055.69     10222203.11      2813416.36     10221973.23
      2814055.68     10221403.12
#Sta/Elev= 30
  4572.3 1102.68  4738.3 1097.16    4877 1089.89  4934.5 1082.41  4940.5 1086.07
  4949.8  1084.8  4955.7  1085.5  4963.6  1084.2  4975.2 1079.76  4975.7 1079.26
  4997.1 1079.76  5013.4 1080.19    5021 1085.57  5027.7 1086.95  5035.2  1090.2
  5056.1 1091.57  5148.1 1093.02    5439 1089.73    5495 1090.88    5531 1094.04
  5554.9  1094.8  5573.6 1096.36  5587.8 1096.24  5608.7 1098.31    5658 1099.36
  5708.2 1102.88  5717.4 1102.63  5750.7 1104.91  5814.4 1105.97  5856.6 1105.48
#Mann= 6 ,-1 , 0
  4572.3     .05       0  4975.2     .05       0  4997.1     .05       0
  5554.9     .12       0  5717.4     .05       0  5750.7     .12       0
Bank Sta=4975.2,4997.1
XS Rating Curve= 0 ,0
Exp/Cntr=0.3,0.1

Type RM Length L Ch R = 1 ,26301   ,852,852,852
BEGIN DESCRIPTION:
Mapping XS e5ad7cdc
END DESCRIPTION:
XS GIS Cut Line= 4
      2813609.03     10222439.24      2813921.53     10222126.75
      2814046.53     10221803.83      2814046.53     10221517.73
#Sta/Elev= 30
    4402 1108.83  4445.8 1109.04  4453.5 1107.92  4495.9 1106.82    4503 1107.63
    4510 1106.25  4549.4  1104.8  4672.7 1097.39  4737.7  1090.8  4771.7 1088.51
  4799.9 1088.39  4814.1 1086.54  4848.6 1086.61  4921.1 1082.78  4926.5 1083.38
  4944.3 1082.23  4951.1 1080.28    4981 1080.63  4994.6 1077.32  4995.1 1076.82
  5016.5 1077.32  5035.5 1081.11  5105.2 1081.46  5126.6 1080.51  5137.4  1083.5
  5144.5 1087.96  5220.9 1088.97  5260.9 1090.89  5350.9 1101.98  5476.3 1108.57
#Mann= 6 ,-1 , 0
    4402     .12       0  4445.8     .05       0  4549.4     .12       0
  4737.7     .05       0  4994.6     .03       0  5016.5     .05       0
Bank Sta=4994.6,5016.5
XS Rating Curve= 0 ,0
Exp/Cntr=0.3,0.1

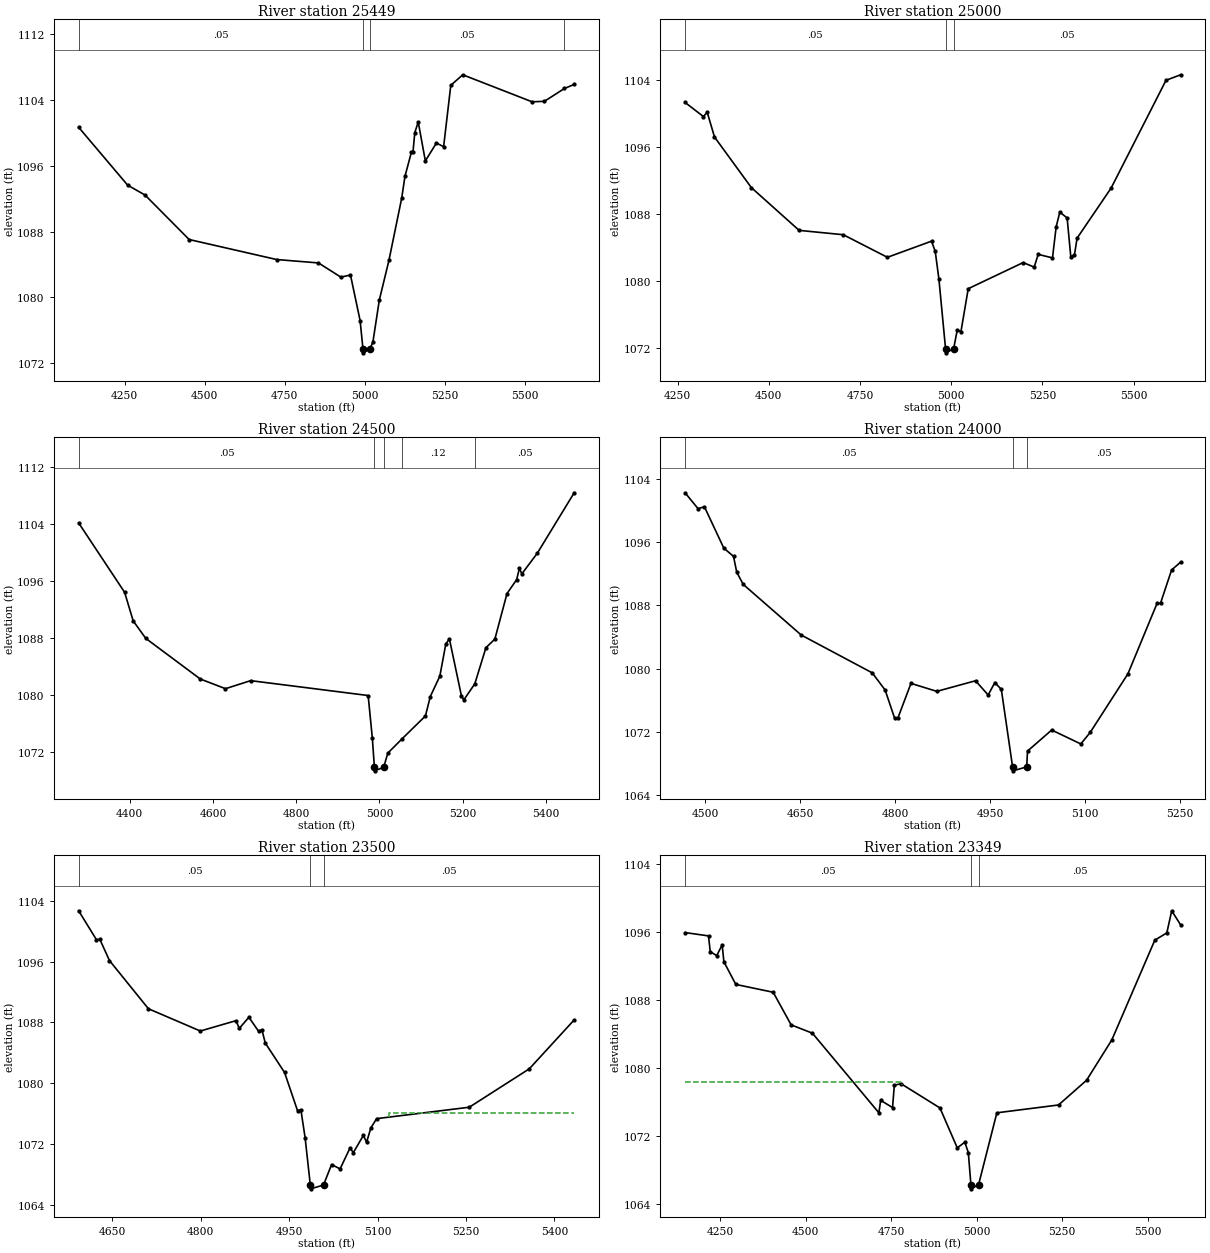
Type RM Length L Ch R = 1 ,25449   ,449,449,449
BEGIN DESCRIPTION:
Mapping XS 83078ae0
END DESCRIPTION:
XS GIS Cut Line= 4
      2813791.31     10222397.59      2814270.49     10222142.37
      2814770.49       10222158.      2815218.41     10221928.83
#Sta/Elev= 30
  4106.8 1100.65  4259.7 1093.63  4314.2 1092.42  4451.7 1087.03  4724.9  1084.6
    4855 1084.19    4925 1082.47  4955.1 1082.72  4985.1  1077.2    4994 1073.78
  4994.5 1073.28  5016.2 1073.78  5025.1  1074.6  5045.1 1079.69  5075.1  1084.5
  5115.1 1092.09  5125.1  1094.7  5145.1 1097.61    5150 1097.61  5155.8 1100.01
  5166.5 1101.29  5188.7 1096.57  5223.2 1098.74  5245.7 1098.29  5268.1 1105.74
  5305.4 1107.02  5521.9 1103.74  5560.2  1103.8  5622.9 1105.36  5653.1 1105.85
#Mann= 4 ,-1 , 0
  4106.8     .05       0    4994     .05       0  5016.2     .05       0
  5622.9     .12       0
Bank Sta=4994,5016.2
XS Rating Curve= 0 ,0
Exp/Cntr=0.3,0.1

Type RM Length L Ch R = 1 ,25000   ,500,500,500
BEGIN DESCRIPTION:
OATMAN CREEK 49.0
END DESCRIPTION:
XS GIS Cut Line= 3
      2813855.72     10222503.12      2814578.92     10222597.28
      2815205.64     10222653.11
#Sta/Elev= 30
  4270.7 1101.34  4321.1 1099.65  4331.2 1100.19  4351.3 1097.21  4452.2 1091.17
  4583.3 1086.05  4704.3 1085.53  4825.3 1082.83  4946.3 1084.76  4956.4 1083.54
  4966.5 1080.24  4984.7 1071.91  4985.2 1071.41  5006.9 1071.91  5016.8 1074.14
  5026.9 1073.94  5046.9 1079.08  5197.5  1082.2  5227.7 1081.66  5238.7 1083.18
  5277.9 1082.76  5287.9 1086.46  5297.9 1088.23    5318 1087.54  5328.1 1082.89
  5338.1 1083.11  5345.3 1085.12  5438.5  1091.1  5589.1 1103.99  5629.2 1104.65
#Mann= 3 ,-1 , 0
  4270.7     .05       0  4984.7     .05       0  5006.9     .05       0
Bank Sta=4984.7,5006.9
XS Rating Curve= 0 ,0
Exp/Cntr=0.3,0.1

Type RM Length L Ch R = 1 ,24500   ,500,500,500
BEGIN DESCRIPTION:
OATMAN CREEK 48.0
END DESCRIPTION:
XS GIS Cut Line= 3
      2813855.73     10223003.12      2814572.57     10223097.24
      2814805.71     10223503.15
#Sta/Elev= 30
    4277 1104.12  4387.5 1094.37  4408.1 1090.36  4438.3  1087.9  4569.4 1082.19
    4630 1080.83  4690.5 1081.96  4972.9 1079.87    4983 1073.86  4987.9 1069.79
  4988.4 1069.29  5010.2 1069.79  5020.2 1071.78  5053.6 1073.74  5110.6    1077
  5122.3 1079.73  5145.2 1082.59  5159.6 1087.12  5168.2 1087.82    5197 1079.85
  5202.8 1079.25  5229.3 1081.52    5256 1086.59  5277.5  1087.8  5306.6 1094.19
  5329.7 1096.14  5336.5 1097.73  5342.3 1096.96  5379.6 1099.87  5468.1 1108.35
#Mann= 5 ,-1 , 0
    4277     .05       0  4987.9     .05       0  5010.2     .05       0
  5053.6     .12       0  5229.3     .05       0
Bank Sta=4987.9,5010.2
XS Rating Curve= 0 ,0
Exp/Cntr=0.3,0.1

Type RM Length L Ch R = 1 ,24000   ,500,500,500
BEGIN DESCRIPTION:
OATMAN CREEK 47.0
END DESCRIPTION:
XS GIS Cut Line= 3
      2813755.64     10223503.12      2814277.48     10223398.61
      2814505.69     10223503.11
#Sta/Elev= 30
  4467.8 1102.23  4488.2 1100.23  4498.4 1100.45    4529 1095.23  4544.3 1094.19
  4549.4  1092.2  4559.6 1090.65  4651.4 1084.24  4763.6 1079.46    4784 1077.28
  4799.1 1073.69  4804.4 1073.81  4824.8 1078.13  4865.6 1077.12  4926.8 1078.46
  4946.8 1076.66  4957.4 1078.24  4967.6 1077.36  4985.4 1067.57  4985.9 1067.07
  5007.7 1067.57    5009 1069.57  5047.2 1072.23  5093.2 1070.47    5108 1071.92
  5167.7 1079.34  5213.7 1088.24  5219.2 1088.26  5236.7 1092.47    5251 1093.46
#Mann= 3 ,-1 , 0
  4467.8     .05       0  4985.4     .05       0  5007.7     .05       0
Bank Sta=4985.4,5007.7
XS Rating Curve= 0 ,0
Exp/Cntr=0.3,0.1

Type RM Length L Ch R = 1 ,23500   ,151,151,151
BEGIN DESCRIPTION:
OATMAN CREEK 46.0
END DESCRIPTION:
XS GIS Cut Line= 3
      2813755.66      10223653.1        2814116.     10223842.97
      2814505.71      10223653.1
#Sta/Elev= 30
  4592.7 1102.68  4622.9 1098.88  4628.6 1098.94    4645 1096.14  4711.1  1089.8
  4799.2 1086.87  4859.6 1088.23  4865.3 1087.22  4881.6 1088.68  4897.9 1086.85
  4903.7 1087.03  4909.3  1085.3  4942.1 1081.42  4964.1  1076.4  4969.8 1076.52
    4977 1072.83  4985.8 1066.62  4986.3 1066.12  5008.2 1066.62  5021.9 1069.32
  5036.3 1068.74  5053.2  1071.5  5058.8 1070.88  5075.8 1073.14  5081.3 1072.25
  5088.6 1074.14  5098.3 1075.35  5255.5 1076.85  5357.4  1081.9  5433.5 1088.33
#Mann= 3 ,-1 , 0
  4592.7     .05       0  4985.8     .03       0  5008.2     .05       0
#XS Ineff= 2 , 0
                          5118.5         1076.12
Permanent Ineff=
       F       F
Bank Sta=4985.8,5008.2
XS Rating Curve= 0 ,0
Exp/Cntr=0.3,0.1

Type RM Length L Ch R = 1 ,23349   ,349,349,349
BEGIN DESCRIPTION:
Mapping XS 27225c24
END DESCRIPTION:
XS GIS Cut Line= 4
      2813286.46      10224216.4      2814106.79     10223995.04
      2814523.46     10223799.73      2814627.66     10223708.55
#Sta/Elev= 30
  4147.6 1095.91    4216 1095.52  4221.1 1093.67    4240  1093.2  4255.9 1094.46
    4261 1092.48  4295.8 1089.82  4405.1  1088.9  4457.5 1085.07  4519.7 1084.09
    4714 1074.74  4719.2 1076.21  4753.9 1075.35  4759.1 1077.98  4778.6 1078.16
  4892.5 1075.31  4943.1 1070.62  4965.1 1071.29  4975.4 1070.06  4982.9 1066.31
  4983.4 1065.81  5005.4 1066.31  5058.8 1074.74    5239 1075.66  5320.9 1078.56
  5394.9 1083.31  5520.4 1095.02  5555.5 1095.87  5569.8 1098.47  5595.9 1096.81
#Mann= 3 ,-1 , 0
  4147.6     .05       0  4982.9     .03       0  5005.4     .05       0
#XS Ineff= 2 , 0
         4782.45 1078.33
Permanent Ineff=
       F       F
Bank Sta=4982.9,5005.4
XS Rating Curve= 0 ,0
Exp/Cntr=0.3,0.1

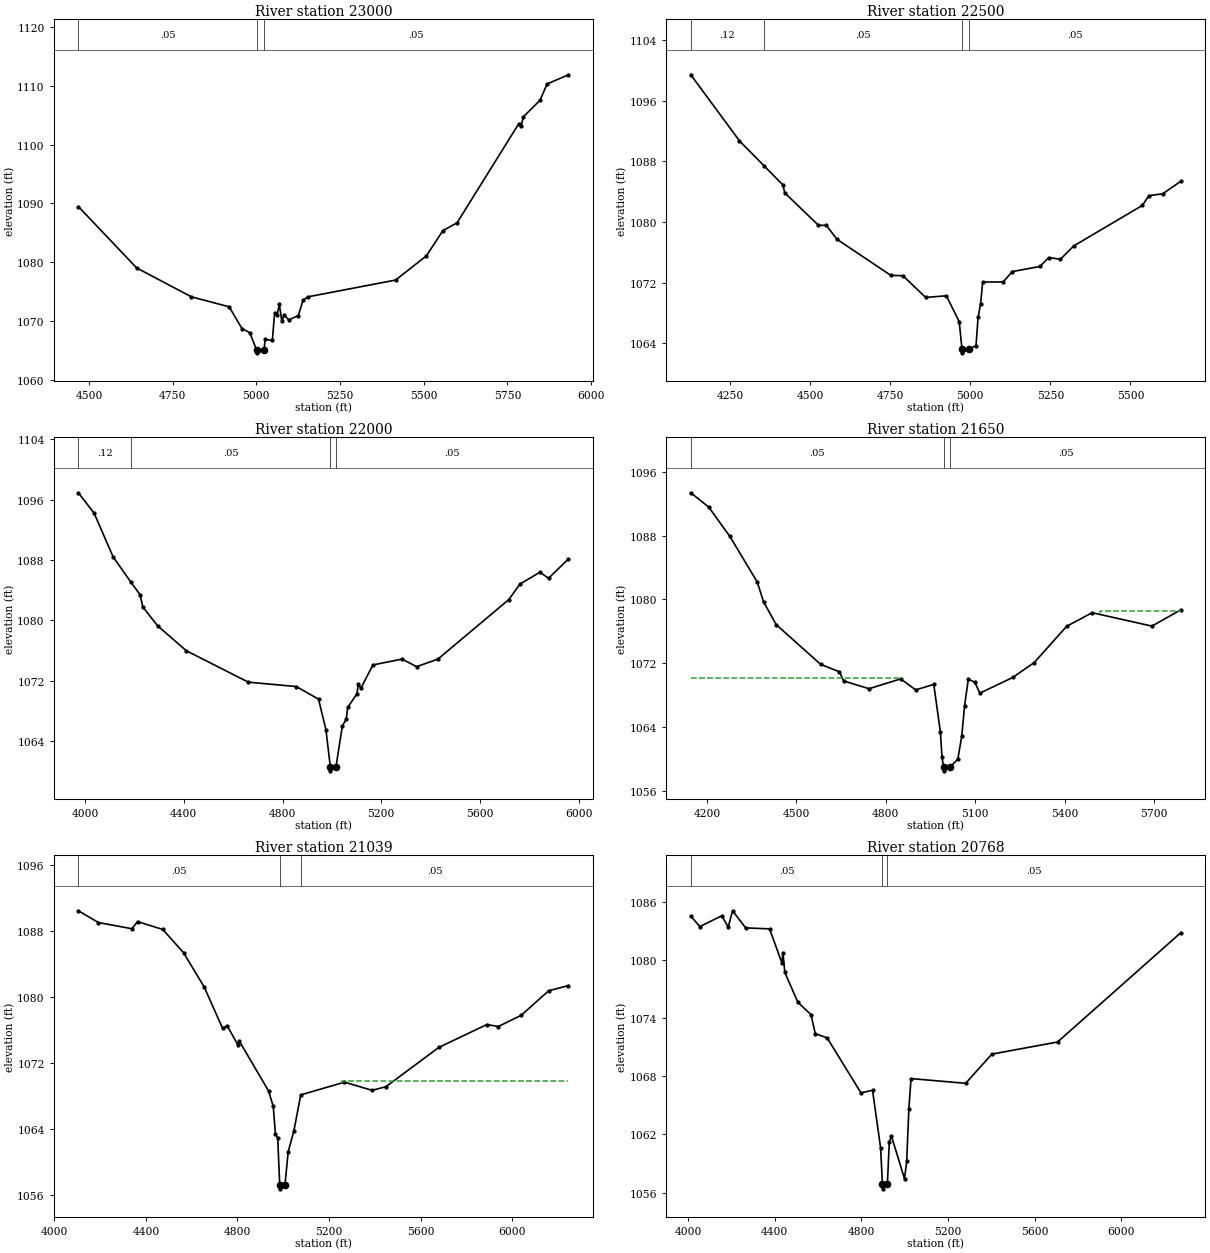
Type RM Length L Ch R = 1 ,23000   ,500,500,500
BEGIN DESCRIPTION:
OATMAN CREEK 45.0
END DESCRIPTION:
XS GIS Cut Line= 3
      2813605.66     10224453.12      2814124.97     10224339.49
      2814755.71     10223653.08
#Sta/Elev= 30
  4468.4 1089.48  4642.5 1079.05  4806.2 1074.14  4918.8 1072.45  4957.2 1068.74
  4980.3 1068.06  5000.7 1065.13  5001.2 1064.63  5023.2 1065.13  5026.1 1066.91
  5047.7 1066.73  5054.5 1071.32  5061.9 1071.04  5068.7 1072.85  5076.1 1069.97
  5082.9 1071.06    5097 1070.23  5125.4 1070.97  5139.6 1073.57  5153.8 1074.14
  5415.8 1076.99  5507.7 1081.09    5557 1085.38  5599.5 1086.72  5783.3 1103.51
  5790.7 1103.15  5797.4 1104.72  5847.4 1107.54  5868.3  1110.3  5932.2 1111.86
#Mann= 3 ,-1 , 0
  4468.4     .05       0  5000.7     .05       0  5023.2     .05       0
Bank Sta=5000.7,5023.2
XS Rating Curve= 0 ,0
Exp/Cntr=0.3,0.1

Type RM Length L Ch R = 1 ,22500   ,500,500,500
BEGIN DESCRIPTION:
OATMAN CREEK 44.0
END DESCRIPTION:
XS GIS Cut Line= 3
      2813455.67     10224553.11      2814288.41     10224811.16
      2814705.66     10224303.14
#Sta/Elev= 30
  4128.2 1099.39  4280.1 1090.68  4355.9 1087.43  4415.7 1084.87  4421.3 1083.83
    4526 1079.58  4551.4 1079.53    4584 1077.72  4752.2 1072.96    4790 1072.91
  4861.1 1070.05  4925.6 1070.27  4965.7 1066.86  4974.3 1063.25  4974.8 1062.75
  4996.8 1063.25  5018.1 1063.71  5024.6 1067.44  5032.5 1069.25  5038.9 1072.08
  5102.8 1072.09  5131.5 1073.46  5217.5 1074.13  5244.9 1075.31  5281.4 1075.08
  5323.1 1076.84  5536.9 1082.17  5557.7 1083.46  5600.8 1083.71  5657.4 1085.37
#Mann= 4 ,-1 , 0
  4128.2     .12       0  4355.9     .05       0  4974.3     .05       0
  4996.8     .05       0
Bank Sta=4974.3,4996.8
XS Rating Curve= 0 ,0
Exp/Cntr=0.3,0.1

Type RM Length L Ch R = 1 ,22000   ,350,350,350
BEGIN DESCRIPTION:
OATMAN CREEK 43.0
END DESCRIPTION:
XS GIS Cut Line= 3
      2813405.73     10225203.12      2814429.67     10225284.99
      2814905.66     10224453.15
#Sta/Elev= 30
  3972.8 1096.89  4036.7 1094.19  4113.2 1088.44  4185.7 1085.06  4223.5 1083.38
  4233.6  1081.8  4293.8  1079.3  4410.5 1075.99  4661.4 1071.84  4855.6 1071.26
  4945.8 1069.59  4975.9 1065.54  4993.7 1060.61  4994.2 1060.11  5016.3 1060.61
  5042.4 1066.05  5058.2 1066.95    5064  1068.5  5101.4  1070.3  5107.2 1071.64
  5117.2 1071.03  5166.2 1074.12  5284.2 1074.89  5343.2 1073.89  5429.5 1074.89
  5716.5 1082.76    5762 1084.82  5842.6 1086.38  5877.8 1085.59  5958.4 1088.14
#Mann= 4 ,-1 , 0
  3972.8     .12       0  4185.7     .05       0  4993.7     .05       0
  5016.3     .05       0
#XS Ineff= 2 , 0
                         5282.92         1074.87
Permanent Ineff=
       F       F
Bank Sta=4993.7,5016.3
XS Rating Curve= 0 ,0
Exp/Cntr=0.3,0.1

Type RM Length L Ch R = 1 ,21650   ,611,611,611
BEGIN DESCRIPTION:
Mapping XS 713cd612
END DESCRIPTION:
XS GIS Cut Line= 4
      2813947.59     10226210.06      2814489.24      10225720.5
      2814671.53     10225371.54       2814780.8     10224861.62
#Sta/Elev= 30
  4145.2 1093.38  4205.5 1091.58  4276.5  1087.9  4368.4 1082.18  4389.4 1079.71
  4431.9 1076.84  4580.7 1071.88  4644.2 1070.93  4658.4 1069.78  4743.6 1068.81
  4849.7 1070.04  4900.3 1068.66  4960.9 1069.35    4983 1063.39  4988.6 1060.19
  4993.6 1059.01  4994.1 1058.51  5016.5 1059.01  5041.6 1059.99  5054.9 1062.89
  5064.2 1066.65  5076.9 1070.02    5099  1069.6  5115.5 1068.25  5225.9 1070.22
  5298.1 1072.09  5406.8 1076.63  5492.4 1078.34  5693.2 1076.66  5790.5 1078.71
#Mann= 3 ,-1 , 0
  4145.2     .05       0  4993.6     .05       0  5016.5     .05       0
#XS Ineff= 2 , 0
         4849.22 1070.09 5517.87         1078.54
Permanent Ineff=
       F       F
Bank Sta=4993.6,5016.5
XS Rating Curve= 0 ,0
Exp/Cntr=0.3,0.1

Type RM Length L Ch R = 1 ,21039   ,271,271,271
BEGIN DESCRIPTION:
Mapping XS aaa7de84
END DESCRIPTION:
XS GIS Cut Line= 4
       2815030.9     10226850.68      2814957.99     10226006.95
      2814890.28     10225361.12      2814885.08     10224716.68
#Sta/Elev= 30
  4105.2 1090.46  4193.1 1089.03  4339.3 1088.28  4363.7 1089.15  4474.1 1088.19
  4564.5 1085.37  4654.8 1081.21  4735.1 1076.19  4755.2 1076.52  4802.5 1074.13
  4807.5 1074.67  4935.9 1068.59  4956.5  1066.7    4966 1063.36    4976 1062.83
  4984.7  1057.2  4985.2  1056.7  5007.6  1057.2  5021.7 1061.19  5046.4 1063.72
  5076.6 1068.11  5267.6 1069.65  5388.3 1068.66  5448.6  1069.1  5679.5 1073.87
  5889.5 1076.65  5939.5 1076.41  6039.5 1077.77  6159.5 1080.75  6245.9 1081.38
#Mann= 3 ,-1 , 0
  4105.2     .05       0  4984.7     .05       0  5076.6     .05       0
#XS Ineff= 2 , 0
                         5257.84          1069.8
Permanent Ineff=
       F       F
Bank Sta=4984.7,5007.6
XS Rating Curve= 0 ,0
Exp/Cntr=0.3,0.1

Type RM Length L Ch R = 1 ,20768   ,688,688,688
BEGIN DESCRIPTION:
Mapping XS 1f448d70
END DESCRIPTION:
XS GIS Cut Line= 4
      2815291.32      10226835.1      2815181.95     10225704.87
      2815062.16     10224871.54      2815072.52     10224586.64
#Sta/Elev= 30
  4012.7 1084.56  4054.9  1083.5  4155.4 1084.61  4185.5 1083.45  4205.6 1085.13
  4265.9 1083.36  4376.4 1083.26  4433.1 1079.75  4438.2  1080.8  4446.7 1078.76
    4507 1075.67  4567.3  1074.4  4587.4 1072.43  4642.4 1071.98  4798.3  1066.3
  4851.7 1066.57  4888.8 1060.63  4897.4 1056.88  4897.9 1056.38  4920.3 1056.88
    4929 1061.25    4939 1061.83  4999.3 1057.41  5009.3 1059.22  5019.4 1064.67
  5029.4 1067.78  5281.3 1067.29  5402.6 1070.31  5705.6 1071.56  6275.2 1082.87
#Mann= 3 ,-1 , 0
  4012.7     .05       0  4897.4     .05       0  4920.3     .05       0
Bank Sta=4897.4,4920.3
XS Rating Curve= 0 ,0
Exp/Cntr=0.3,0.1

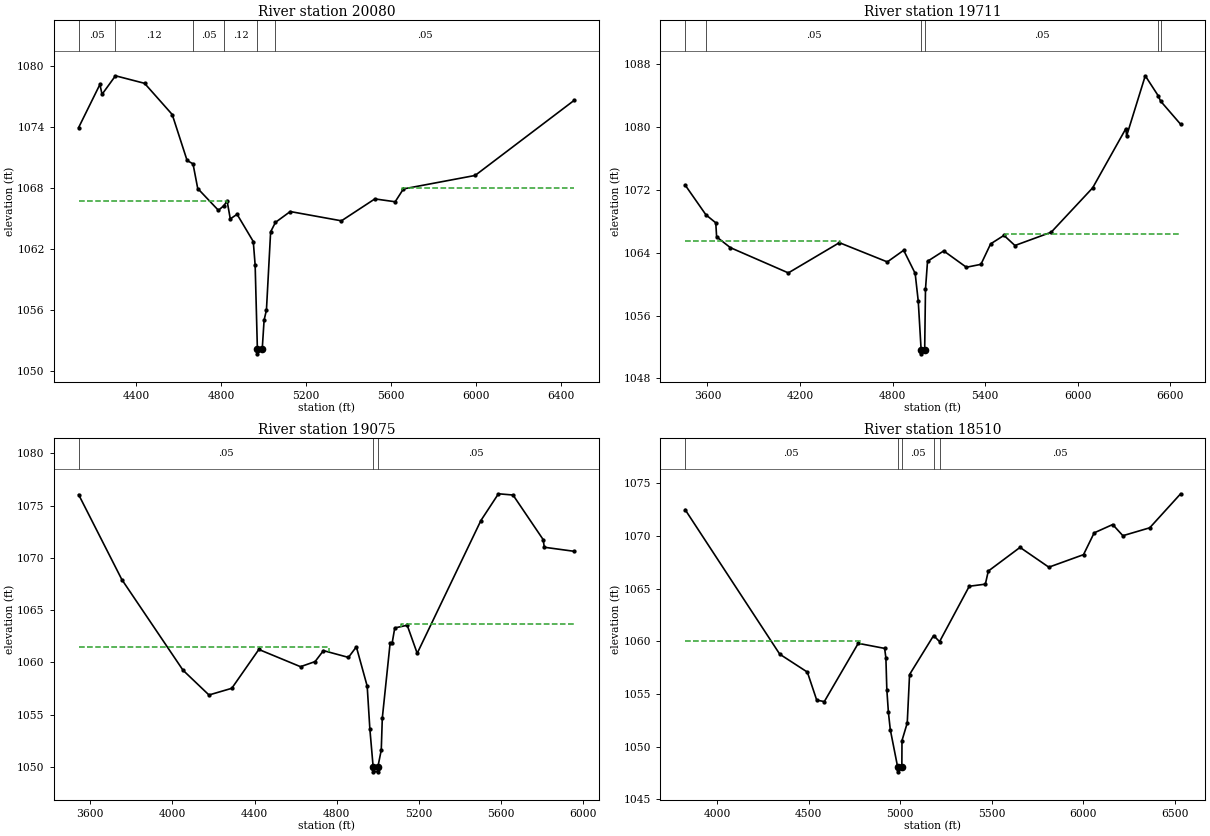
Type RM Length L Ch R = 1 ,20080   ,369,369,369
BEGIN DESCRIPTION:
Mapping XS 9c23fe6b
END DESCRIPTION:
XS GIS Cut Line= 4
      2815924.03     10226813.18      2815924.03     10226153.41
      2815594.16     10225233.27      2815333.74      10224590.9
#Sta/Elev= 30
  4130.9 1073.92    4231 1078.15    4241 1077.18  4304.1    1079    4441 1078.26
    4571  1075.2    4641 1070.69  4668.8 1070.36    4691 1067.94  4788.3  1065.8
  4813.4 1066.25  4829.2 1066.71  4844.1 1064.96    4876 1065.41  4952.2 1062.74
    4961 1060.43  4971.5 1052.22    4972 1051.72  4994.4 1052.22  5003.1 1055.03
  5014.1 1056.01  5033.8 1063.69  5056.6 1064.62  5126.1 1065.68  5366.8 1064.77
    5524 1066.92  5619.6 1066.64  5658.3  1067.9  5995.3 1069.22  6461.3 1076.59
#Mann= 6 ,-1 , 0
  4130.9     .05       0  4304.1     .12       0  4668.8     .05       0
  4813.4     .12       0  4971.5     .05       0  5056.6     .05       0
#XS Ineff= 2 , 0
         4830.72 1066.68  5653.6         1067.98
Permanent Ineff=
       F       F
Bank Sta=4971.5,4994.4
XS Rating Curve= 0 ,0
Exp/Cntr=0.3,0.1

Type RM Length L Ch R = 1 ,19711   ,636,636,636
BEGIN DESCRIPTION:
Mapping XS 91b504b6
END DESCRIPTION:
XS GIS Cut Line= 4
      2815976.14     10227229.79      2816305.97     10227125.64
      2816219.16       10225893.      2815698.38     10224347.99
#Sta/Elev= 30
  3454.8 1072.65  3589.8 1068.85  3653.6 1067.83  3659.2 1066.04    3748 1064.67
    4124 1061.45  4454.8  1065.3  4765.6 1062.85  4871.6 1064.33    4946 1061.39
  4966.1 1057.84  4984.7 1051.64  4985.2 1051.14  5007.7 1051.64    5013 1059.38
  5026.2 1062.93  5131.2 1064.25  5277.9 1062.17  5372.3 1062.54  5435.3 1065.15
  5521.7 1066.23  5592.7 1064.94  5827.7 1066.63  6096.4 1072.28  6311.5 1079.82
  6316.8 1078.91  6437.5 1086.56  6521.9    1084  6536.6 1083.34  6666.8 1080.38
#Mann= 6 ,-1 , 0
  3454.8     .12       0  3589.8     .05       0  4984.7     .05       0
  5007.7     .05       0  6521.9     .12       0  6536.6     .05       0
#XS Ineff= 2 , 0
         4460.81 1065.52 5526.65         1066.46
Permanent Ineff=
       F       F
Bank Sta=4984.7,5007.7
XS Rating Curve= 0 ,0
Exp/Cntr=0.3,0.1

Type RM Length L Ch R = 1 ,19075   ,565,565,565
BEGIN DESCRIPTION:
Mapping XS 313728ca
END DESCRIPTION:
XS GIS Cut Line= 2
      2816566.38     10227438.15       2816965.7     10225059.63
#Sta/Elev= 30
  3543.4 1076.06  3753.5 1067.93  4051.5 1059.24  4177.8 1056.87  4288.7 1057.51
  4420.5 1061.23  4623.3 1059.58  4694.3 1060.07  4734.9 1061.12  4856.6 1060.47
  4895.1 1061.48  4947.8 1057.72  4960.8 1053.62  4976.7 1050.01  4977.2 1049.51
  4999.6 1049.51  5000.1 1050.01  5016.3  1051.6  5021.4 1054.66  5059.4 1061.84
  5069.5 1061.87    5082 1063.29  5142.6 1063.55  5191.2 1060.86  5501.3 1073.58
  5586.6 1076.14  5657.6 1076.02  5804.4 1071.75  5809.7 1071.02  5955.2 1070.63
#Mann= 3 ,-1 , 0
  3543.4     .05       0  4976.7     .05       0  5000.1     .05       0
#XS Ineff= 2 , 0
         4761.76 1061.43 5114.42          1063.7
Permanent Ineff=
       F       F
Bank Sta=4976.7,5000.1
XS Rating Curve= 0 ,0
Exp/Cntr=0.3,0.1

Type RM Length L Ch R = 1 ,18510   ,1947,1947,1947
BEGIN DESCRIPTION:
Mapping XS 84dc83b3
END DESCRIPTION:
XS GIS Cut Line= 3
      2816826.79     10227611.79      2817226.11     10225997.16
      2817434.43      10224972.9
#Sta/Elev= 30
  3823.8  1072.5  4341.2 1058.77    4492 1057.07  4543.2 1054.41  4584.7 1054.27
  4770.2  1059.8  4914.4 1059.32  4921.3 1058.42  4926.4 1055.41    4935 1053.25
  4945.3 1051.61  4985.1  1048.1  4985.6  1047.6  5008.5  1048.1  5009.3 1050.57
    5038 1052.24  5050.7 1056.84  5182.2 1060.54  5214.6 1059.96    5377 1065.22
    5465 1065.42  5480.9 1066.66  5654.5 1068.91  5811.9 1067.03  6001.4 1068.22
  6059.7 1070.29  6160.9 1071.08  6216.6 1070.02  6363.3 1070.77  6532.3    1074
#Mann= 5 ,-1 , 0
  3823.8     .05       0  4985.1     .05       0  5008.5     .05       0
  5182.2     .12       0  5214.6     .05       0
#XS Ineff= 2 , 0
          4783.7 1060.05
Permanent Ineff=
       F       F
Bank Sta=4985.1,5008.5
XS Rating Curve= 0 ,0
Exp/Cntr=0.3,0.1