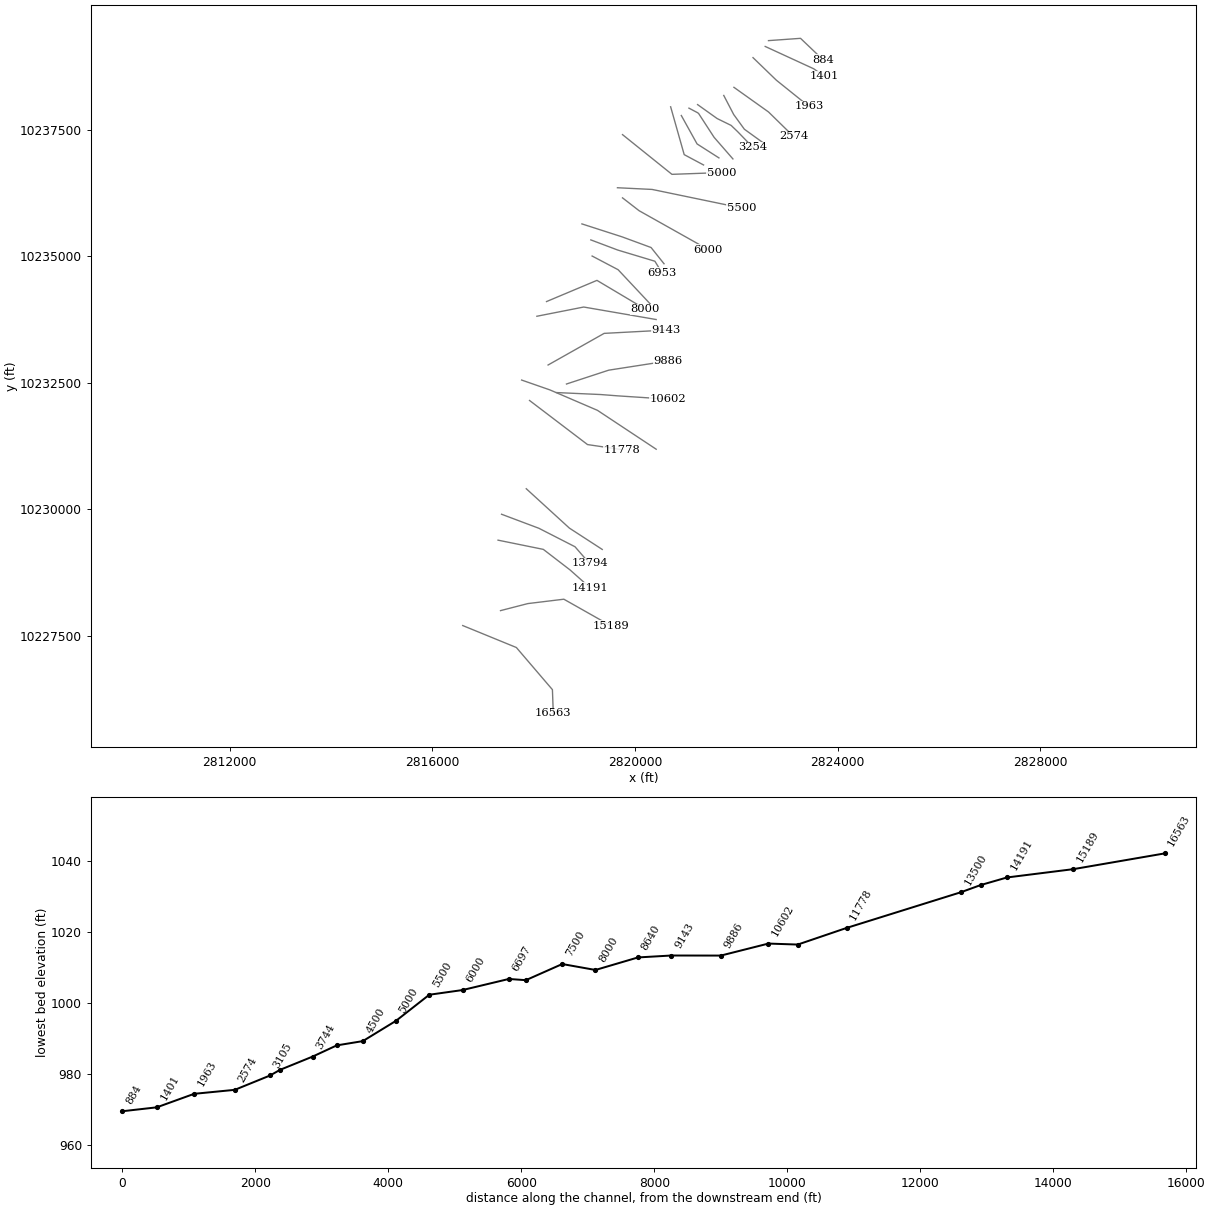
HEC-RAS study OATMAN CREEK.prj: OATMAN CREEK Base Level Engineering

--- OATMAN CREEK.g01 (geometry) --- (continued)

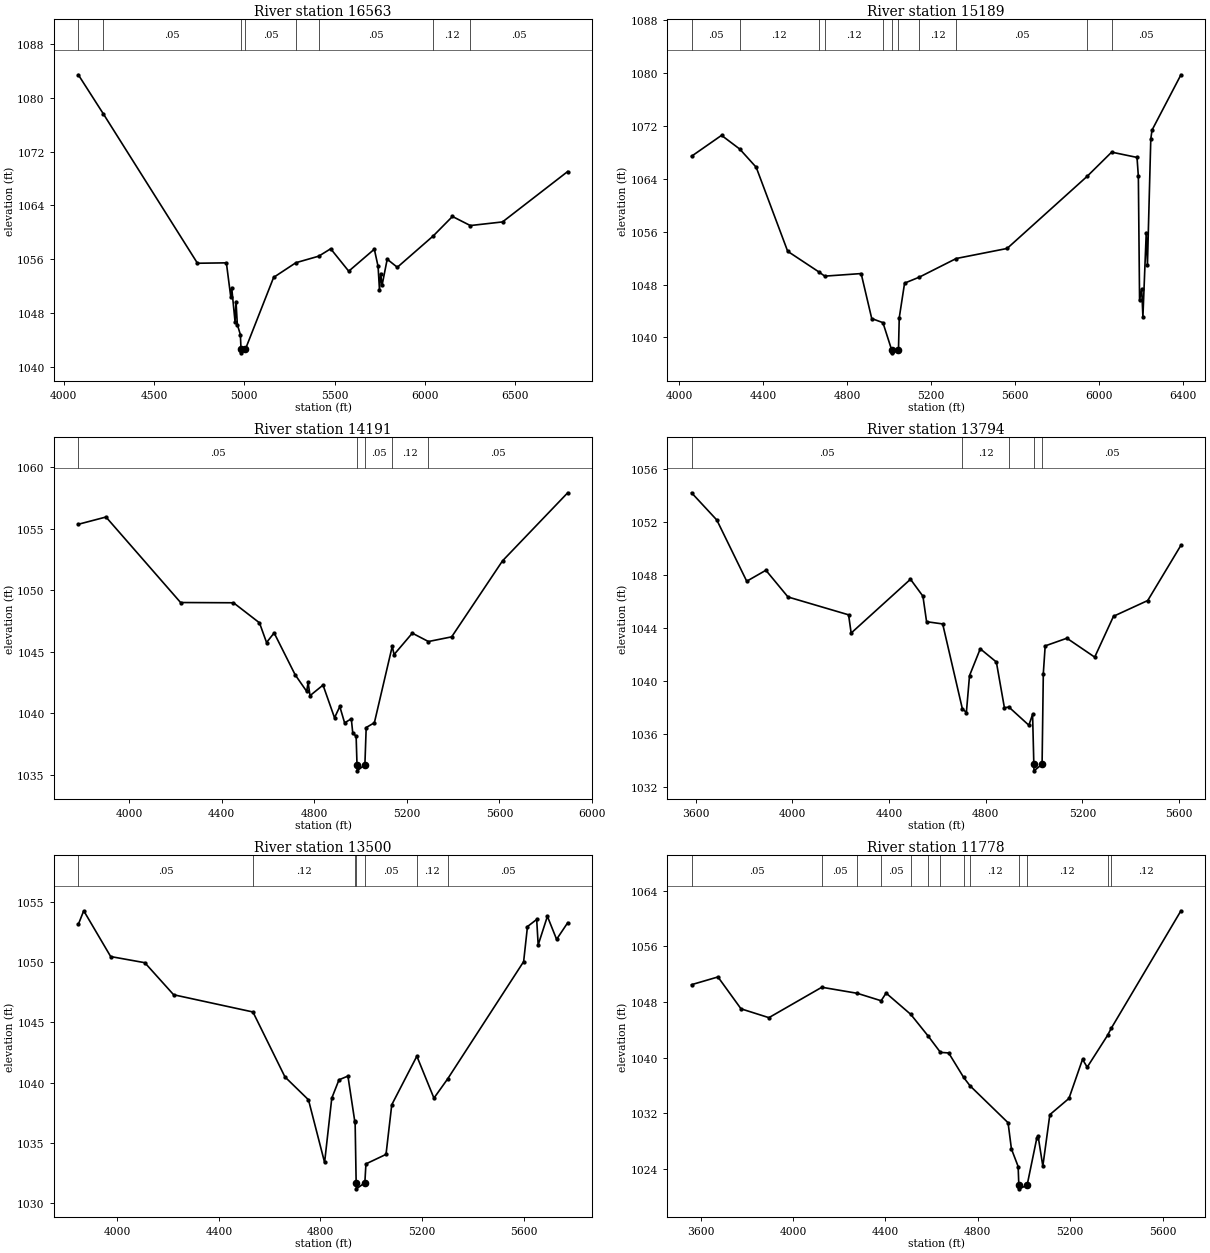
Type RM Length L Ch R = 1 ,16563   ,1374,1374,1374
BEGIN DESCRIPTION:
Mapping XS 502abe1c
END DESCRIPTION:
XS GIS Cut Line= 4
      2816601.15     10227698.54      2817660.14     10227264.52
      2818371.94     10226431.19       2818389.3     10225962.44
#Sta/Elev= 30
  4081.1 1083.41    4219 1077.63  4740.7 1055.41  4900.8 1055.47  4924.8 1050.47
  4930.2 1051.79  4948.8 1046.72  4954.2 1049.72  4961.4  1046.3  4978.2 1044.81
    4982  1042.6  4982.5  1042.1  5005.6  1042.6  5162.4 1053.31  5285.7 1055.49
    5412 1056.46  5478.3 1057.56  5578.2 1054.23  5719.9  1057.5  5740.7 1054.94
  5748.4 1051.46    5755 1053.88  5762.7 1052.13  5791.2 1056.01  5847.2 1054.81
  6046.5 1059.48  6152.4 1062.36  6251.3 1061.01  6429.7 1061.55  6790.6 1069.04
#Mann= 8 ,-1 , 0
  4081.1     .12       0    4219     .05       0    4982     .05       0
  5005.6     .05       0  5285.7     .12       0    5412     .05       0
  6046.5     .12       0  6251.3     .05       0
Bank Sta=4982,5005.6
XS Rating Curve= 0 ,0
Exp/Cntr=0.3,0.1

Type RM Length L Ch R = 1 ,15189   ,998,998,998
BEGIN DESCRIPTION:
Mapping XS 6b8839b7
END DESCRIPTION:
XS GIS Cut Line= 4
      2817347.63     10227993.69      2817885.83     10228132.58
      2818597.64     10228219.39      2819517.74     10227698.57
#Sta/Elev= 30
  4060.3 1067.43  4203.1 1070.59  4289.6 1068.52  4368.1 1065.76    4518 1053.04
  4665.5 1049.94  4694.5 1049.28  4867.8 1049.67  4918.2 1042.86  4971.5 1042.24
  5012.5 1038.17  5013.1 1037.67  5045.6 1038.17  5049.2 1042.97  5074.6 1048.22
  5144.9 1049.13  5320.7 1051.95  5562.8 1053.47  5944.3  1064.4  6060.6 1068.05
  6181.3 1067.25  6187.7  1064.4  6193.5 1045.63  6203.6 1047.37  6209.4 1043.11
  6225.3 1055.87    6231 1051.03  6246.9 1070.02  6252.7 1071.38  6390.5 1079.76
#Mann= 11 ,-1 , 0
  4060.3     .05       0  4289.6     .12       0  4665.5     .05       0
  4694.5     .12       0  4971.5     .05       0  5012.5     .05       0
  5045.6     .05       0  5144.9     .12       0  5320.7     .05       0
  5944.3     .12       0  6060.6     .05       0
Bank Sta=5012.5,5045.6
XS Rating Curve= 0 ,0
Exp/Cntr=0.3,0.1

Type RM Length L Ch R = 1 ,14191   ,397,397,397
BEGIN DESCRIPTION:
Mapping XS 1ca17bfb
END DESCRIPTION:
XS GIS Cut Line= 4
      2817298.48     10229386.62      2818192.54     10229204.34
      2818722.06     10228796.35      2819121.06     10228440.72
#Sta/Elev= 30
  3779.8 1055.37  3899.4 1055.96  4221.9 1049.01  4450.5 1048.99  4562.8 1047.36
  4593.4 1045.76  4626.2 1046.54    4717 1043.14  4766.8 1041.79  4773.1 1042.51
  4781.3 1041.44  4837.5  1042.3  4887.3 1039.64    4910 1040.56  4930.8 1039.23
  4959.8 1039.56  4966.1 1038.39  4980.6 1038.15  4984.4 1035.83    4985 1035.33
  5018.5 1035.83  5024.1 1038.85  5059.5 1039.24  5136.7 1045.45  5144.6 1044.78
  5223.4 1046.52  5293.1 1045.84  5393.6 1046.22  5613.5  1052.4  5895.2 1057.93
#Mann= 5 ,-1 , 0
  3779.8     .05       0  4984.4     .05       0  5018.5     .05       0
  5136.7     .12       0  5293.1     .05       0
Bank Sta=4984.4,5018.5
XS Rating Curve= 0 ,0
Exp/Cntr=0.3,0.1

Type RM Length L Ch R = 1 ,13794   ,294,294,294
BEGIN DESCRIPTION:
Mapping XS a54cd7d8
END DESCRIPTION:
XS GIS Cut Line= 4
       2817367.9     10229898.78      2818105.74     10229621.01
      2818817.54     10229256.42      2819103.33     10228927.33
#Sta/Elev= 30
  3583.5 1054.22    3688 1052.16  3811.7 1047.53    3891 1048.36  3982.3 1046.34
  4232.9 1044.99  4243.6 1043.61  4488.9 1047.68  4540.4  1046.4  4555.5 1044.47
  4622.1  1044.3  4703.4 1037.89  4720.1  1037.6  4733.1 1040.39  4777.5 1042.42
  4844.1 1041.42  4877.3 1037.97  4896.2 1038.01  4978.5 1036.64  4993.9 1037.46
  4999.1 1033.69  4999.7 1033.19  5033.2 1033.69  5038.3 1040.55    5046 1042.64
  5135.8 1043.22  5250.8 1041.79  5328.6 1044.88  5470.1 1046.07  5607.5 1050.25
#Mann= 5 ,-1 , 0
  3583.5     .05       0  4703.4     .12       0  4896.2     .05       0
  4999.1     .05       0  5033.2     .05       0
Bank Sta=4999.1,5033.2
XS Rating Curve= 0 ,0
Exp/Cntr=0.3,0.1

Type RM Length L Ch R = 1 ,13500   ,1722,1722,1722
BEGIN DESCRIPTION:
OATMAN CREEK 27.0
END DESCRIPTION:
XS GIS Cut Line= 3
      2817855.66     10230403.13      2818706.93     10229624.73
      2819355.66     10229203.12
#Sta/Elev= 30
  3846.5 1053.14  3867.8 1054.27  3973.9 1050.47  4108.3 1049.96  4221.8  1047.3
  4534.1 1045.87  4660.2 1040.48  4752.8 1038.58  4816.3 1033.38  4844.6 1038.72
    4873 1040.24  4908.2 1040.55  4934.7 1036.85  4936.5 1036.74  4940.6 1031.69
  4941.3 1031.19  4974.8 1031.69  4979.1 1033.26  5058.2 1034.05  5080.8 1038.17
  5179.6  1042.2  5246.9 1038.72  5300.7 1040.31  5600.1 1050.05  5615.2 1052.96
  5651.5 1053.55  5657.4 1051.44  5693.7 1053.81  5729.9  1051.9  5773.7 1053.28
#Mann= 7 ,-1 , 0
  3846.5     .05       0  4534.1     .12       0  4934.7     .05       0
  4940.6     .03       0  4974.8     .05       0  5179.6     .12       0
  5300.7     .05       0
Bank Sta=4940.6,4974.8
XS Rating Curve= 0 ,0
Exp/Cntr=0.3,0.1

Type RM Length L Ch R = 1 ,11778   ,735,735,735
BEGIN DESCRIPTION:
OATMAN CREEK 24.0
END DESCRIPTION:
XS GIS Cut Line= 3
       2817920.3     10232147.84        2819065.       10231276.
      2819737.15     10231176.98
#Sta/Elev= 30
  3561.1 1050.47  3675.4 1051.58  3775.2    1047  3895.9 1045.73  4124.9  1050.1
  4278.4 1049.23  4381.7 1048.16  4403.1 1049.26    4510  1046.2  4585.4 1043.08
  4638.4 1040.74    4674 1040.66  4738.9 1037.14  4766.7 1035.93  4931.1 1030.63
  4945.6 1026.87  4974.7 1024.34  4977.7 1021.63  4978.5 1021.13  5013.4 1021.63
  5055.2 1028.37  5061.3 1028.67  5081.6 1024.39  5111.9 1031.79  5194.6 1034.12
  5253.4 1039.74  5273.6 1038.61  5361.6 1043.18  5377.3 1044.18  5679.4 1061.09
#Mann= 13 ,-1 , 0
  3561.1     .05       0  4124.9     .05       0  4278.4     .12       0
  4381.7     .05       0    4510     .12       0  4585.4     .05       0
  4638.4     .12       0  4738.9     .05       0  4766.7     .12       0
  4977.7     .07       0  5013.4     .12       0  5361.6     .05       0
  5377.3     .12       0
Bank Sta=4977.7,5013.4
XS Rating Curve= 0 ,0
Exp/Cntr=0.3,0.1

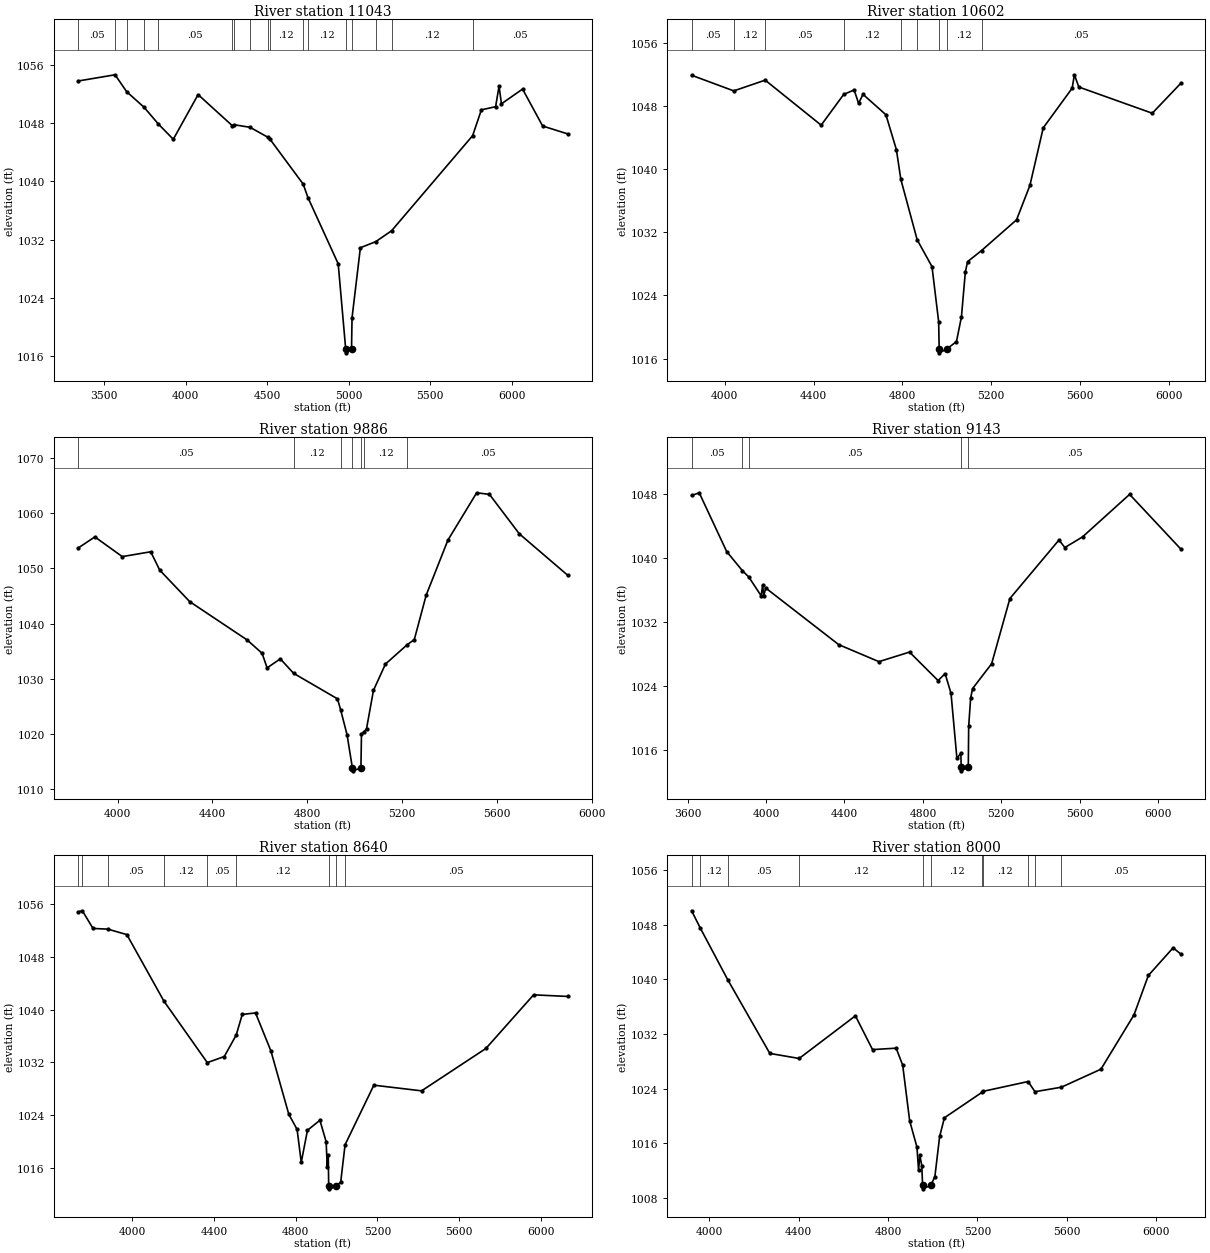
Type RM Length L Ch R = 1 ,11043   ,441,441,441
BEGIN DESCRIPTION:
Mapping XS 28153d28
END DESCRIPTION:
XS GIS Cut Line= 4
      2817764.09     10232551.46      2818323.98     10232356.15
      2819261.48      10231952.5      2820420.29      10231184.3
#Sta/Elev= 30
  3340.7 1053.75  3566.2  1054.6  3637.8 1052.27    3744 1050.15  3831.8 1047.85
  3923.7 1045.75    4076 1051.88  4285.8 1047.62  4298.9 1047.74  4395.3 1047.39
  4504.9 1046.02  4514.7 1045.84  4721.1  1039.6  4750.7 1037.73    4936 1028.67
  4982.1 1016.95  4982.9 1016.45  5017.8 1016.95    5021 1021.26  5072.2 1030.87
  5166.9 1031.71  5263.8  1033.2  5761.3 1046.25  5815.1 1049.79  5902.3 1050.22
  5923.4 1053.03  5938.4 1050.62  6067.8 1052.64  6191.1 1047.57  6344.7 1046.49
#Mann= 17 ,-1 , 0
  3340.7     .05       0  3566.2     .12       0  3637.8     .05       0
    3744     .12       0  3831.8     .05       0  4285.8     .12       0
  4298.9     .05       0  4395.3     .12       0  4504.9     .05       0
  4514.7     .12       0  4721.1     .05       0  4750.7     .12       0
  4982.1     .07       0  5017.8     .12       0  5166.9     .05       0
  5263.8     .12       0  5761.3     .05       0
Bank Sta=4982.1,5017.8
XS Rating Curve= 0 ,0
Exp/Cntr=0.3,0.1

Type RM Length L Ch R = 1 ,10602   ,716,716,716
BEGIN DESCRIPTION:
Mapping XS 0c384993
END DESCRIPTION:
XS GIS Cut Line= 4
      2818454.16     10232304.07      2819326.58       10232265.
      2819665.12     10232238.96      2820654.74     10232173.86
#Sta/Elev= 30
  3850.5 1051.88  4040.5  1049.9    4182 1051.26  4434.2 1045.56  4535.7 1049.45
  4582.8 1050.02  4602.8 1048.32  4622.8 1049.46  4725.9 1046.88    4773 1042.47
  4793.2 1038.69  4866.8 1031.04  4933.5 1027.65  4963.6 1020.66  4965.8 1017.23
  4966.6 1016.73  5001.5 1017.23  5043.8 1018.16  5066.1 1021.27  5083.9    1027
    5094 1028.28  5156.6 1029.68  5314.4 1033.57  5374.6 1037.93  5434.7 1045.22
    5565 1050.24    5575 1051.94    5595 1050.39  5925.8 1047.07  6055.1 1050.88
#Mann= 9 ,-1 , 0
  3850.5     .05       0  4040.5     .12       0    4182     .05       0
  4535.7     .12       0  4793.2     .05       0  4866.8     .12       0
  4965.8     .07       0  5001.5     .12       0  5156.6     .05       0
Bank Sta=4965.8,5001.5
XS Rating Curve= 0 ,0
Exp/Cntr=0.3,0.1

Type RM Length L Ch R = 1 ,9886    ,743,743,743
BEGIN DESCRIPTION:
Mapping XS f8fc1bf5
END DESCRIPTION:
XS GIS Cut Line= 3
       2818649.5     10232473.34      2819482.83     10232746.78
      2820654.69     10232929.06
#Sta/Elev= 30
  3834.4 1053.72  3904.1 1055.71  4019.8 1052.14  4139.6 1053.02  4177.7 1049.69
    4304 1043.99  4546.1 1037.05  4609.2 1034.63  4630.3 1031.99  4685.9 1033.63
    4742 1031.01  4926.9 1026.39  4940.6 1024.35  4967.3 1019.89  4989.9 1013.85
  4990.7 1013.35  5025.8 1013.85  5028.1 1019.99  5039.9 1020.45  5049.4 1020.97
  5078.7 1027.93  5129.3 1032.69  5221.5 1036.21  5250.7  1037.1    5301 1045.17
  5392.4 1055.12  5513.8  1063.7  5567.7 1063.41  5693.5 1056.27  5897.4 1048.77
#Mann= 7 ,-1 , 0
  3834.4     .05       0    4742     .12       0  4940.6     .05       0
  4989.9     .03       0  5025.8     .05       0  5039.9     .12       0
  5221.5     .05       0
Bank Sta=4989.9,5025.8
XS Rating Curve= 0 ,0
Exp/Cntr=0.3,0.1

Type RM Length L Ch R = 1 ,9143    ,503,503,503
BEGIN DESCRIPTION:
Mapping XS 1cf556b2
END DESCRIPTION:
XS GIS Cut Line= 3
      2818286.48     10232849.21      2819393.25     10233474.21
      2820617.17     10233539.31
#Sta/Elev= 30
  3619.9 1047.87  3658.8 1048.21  3798.8 1040.85    3879 1038.45  3911.7 1037.66
    3975 1035.29  3982.2 1036.63    3988 1035.29    3998 1036.28  4370.7 1029.18
  4575.7 1027.05  4731.7 1028.25  4877.5 1024.68  4913.4 1025.55  4943.5 1023.07
  4973.5 1014.94  4993.5 1015.57  4995.6 1013.87  4996.4 1013.37  5031.6 1013.87
  5033.6 1018.94  5043.6  1022.5  5053.6 1023.68  5150.7 1026.79  5243.9 1034.96
  5494.2 1042.29  5524.3 1041.35  5614.4 1042.68  5854.7 1048.01  6116.6 1041.14
#Mann= 5 ,-1 , 0
  3619.9     .05       0    3879     .12       0  3911.7     .05       0
  4995.6     .05       0  5031.6     .05       0
Bank Sta=4995.6,5031.6
XS Rating Curve= 0 ,0
Exp/Cntr=0.3,0.1

Type RM Length L Ch R = 1 ,8640    ,640,640,640
BEGIN DESCRIPTION:
Mapping XS 7b525b34
END DESCRIPTION:
XS GIS Cut Line= 3
      2818065.16     10233812.75       2818989.6     10233995.04
      2820419.98     10233747.97
#Sta/Elev= 30
  3737.1 1054.81  3756.8 1054.97    3809 1052.29  3881.2 1052.19  3974.4 1051.36
    4156 1041.27    4368 1031.96  4451.1 1032.88  4509.5 1036.14    4539 1039.26
    4604 1039.49  4679.3 1033.72  4766.7 1024.13  4807.3 1021.83  4827.6 1016.85
    4858  1021.7  4918.9 1023.22  4949.4 1019.97  4954.7 1016.15  4959.8 1017.99
  4961.8 1013.33  4962.7 1012.83  4997.8 1013.33  5020.4 1013.81    5042 1019.51
  5182.8 1028.54  5416.2 1027.68  5730.8  1034.1  5964.2 1042.23  6130.9 1041.99
#Mann= 9 ,-1 , 0
  3737.1     .05       0  3756.8     .12       0  3881.2     .05       0
    4156     .12       0    4368     .05       0  4509.5     .12       0
  4961.8     .07       0  4997.8     .12       0    5042     .05       0
Bank Sta=4961.8,4997.8
XS Rating Curve= 0 ,0
Exp/Cntr=0.3,0.1

Type RM Length L Ch R = 1 ,8000    ,500,500,500
BEGIN DESCRIPTION:
OATMAN CREEK 16.0
END DESCRIPTION:
XS GIS Cut Line= 3
      2818255.72     10234103.13      2819250.98     10234521.97
      2820205.65     10233953.13
#Sta/Elev= 30
  3920.2 1050.04  3958.3 1047.56  4082.1 1039.93  4270.5 1029.14  4401.7  1028.4
  4653.7 1034.65  4730.3  1029.7  4836.1 1029.91  4865.3 1027.43  4896.6 1019.27
  4929.2 1015.42  4936.5 1012.03    4942 1014.23  4950.9  1012.7  4954.5  1009.8
  4955.4  1009.3  4990.6  1009.8  5009.4 1011.06  5030.8 1016.97  5052.2 1019.71
  5221.7 1023.47  5223.3 1023.57  5426.9 1025.02  5457.7 1023.53  5575.7 1024.19
  5753.1 1026.83  5901.1 1034.79  5965.3 1040.56  6076.3 1044.62  6111.3 1043.68
#Mann= 11 ,-1 , 0
  3920.2     .05       0  3958.3     .12       0  4082.1     .05       0
  4401.7     .12       0  4954.5     .07       0  4990.6     .12       0
  5221.7     .05       0  5223.3     .12       0  5426.9     .05       0
  5457.7     .12       0  5575.7     .05       0
Bank Sta=4954.5,4990.6
XS Rating Curve= 0 ,0
Exp/Cntr=0.3,0.1

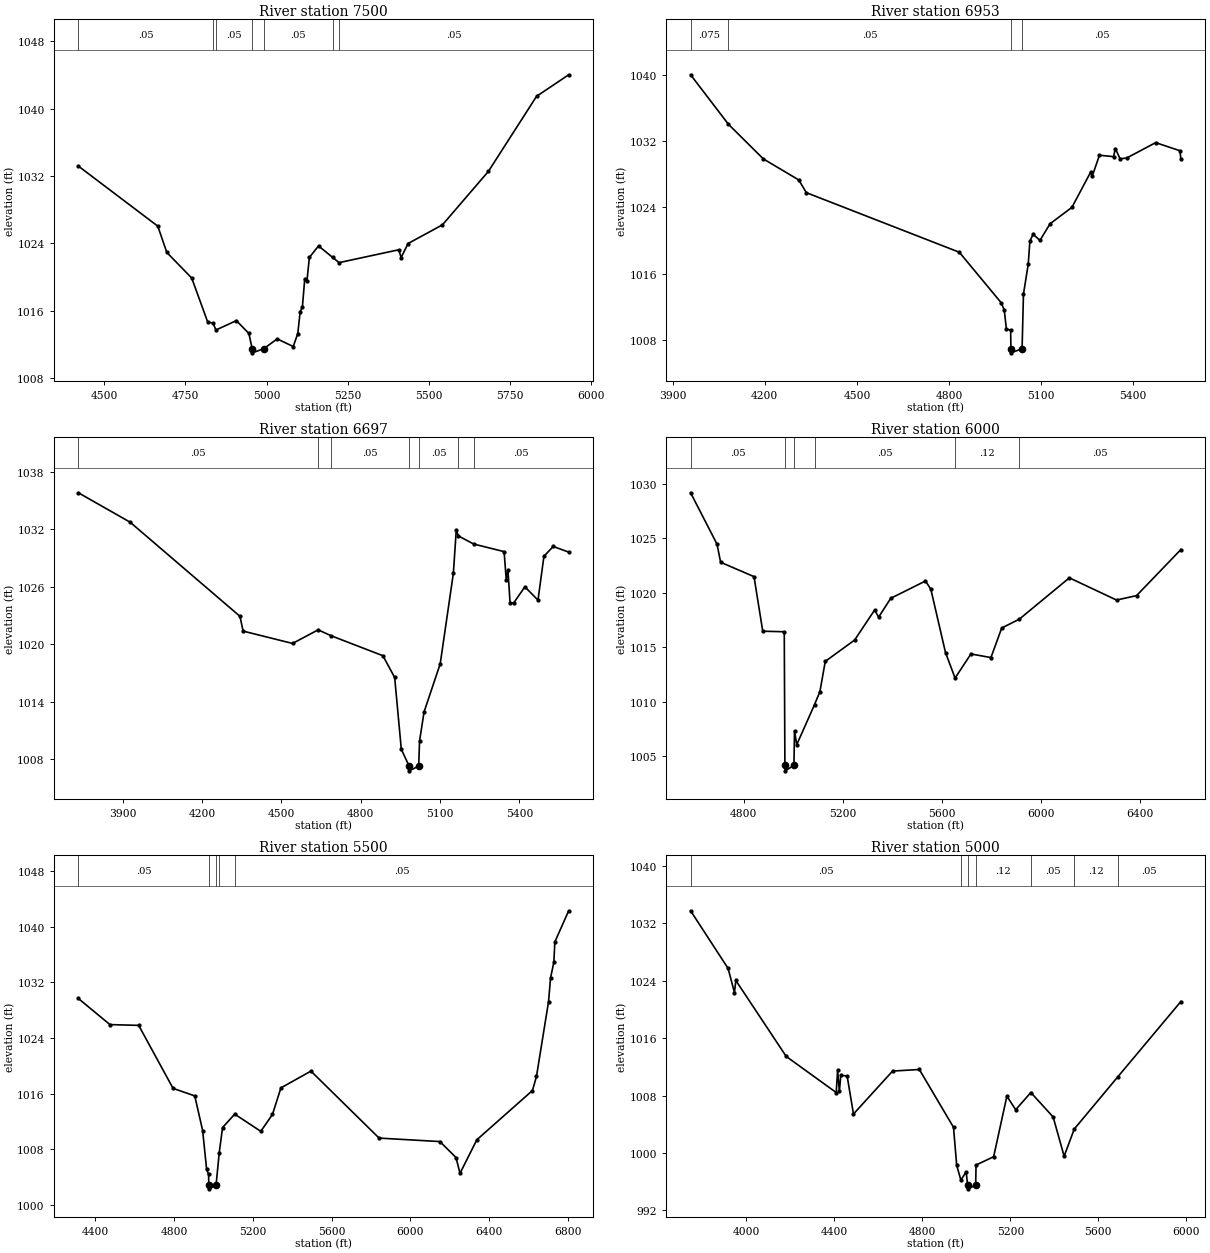
Type RM Length L Ch R = 1 ,7500    ,547,547,547
BEGIN DESCRIPTION:
OATMAN CREEK 15.0
END DESCRIPTION:
XS GIS Cut Line= 3
      2819155.66     10235003.12      2819668.99     10234732.72
      2820305.71     10234053.08
#Sta/Elev= 30
  4419.8 1033.16  4664.7 1026.02  4692.4  1022.9  4769.2 1019.86  4818.9 1014.59
  4834.8 1014.52  4843.9 1013.68    4907  1014.8  4945.5 1013.27  4955.5 1011.47
  4956.4 1010.97  4991.8 1011.47  5032.7 1012.63  5082.1 1011.72  5096.2 1013.26
  5103.5 1015.84  5110.4 1016.39  5117.7 1019.79  5124.6 1019.56  5131.9 1022.31
  5160.2 1023.67    5204  1022.3  5223.5 1021.69  5407.9 1023.22  5414.7 1022.28
  5436.2 1023.96  5542.2 1026.18  5683.8 1032.53  5832.3 1041.45  5931.3 1044.01
#Mann= 7 ,-1 , 0
  4419.8     .05       0  4834.8     .12       0  4843.9     .05       0
  4955.5     .05       0  4991.8     .05       0    5204     .12       0
  5223.5     .05       0
Bank Sta=4955.5,4991.8
XS Rating Curve= 0 ,0
Exp/Cntr=0.3,0.1

Type RM Length L Ch R = 1 ,6953    ,256,256,256
BEGIN DESCRIPTION:
Mapping XS 504cad5b
END DESCRIPTION:
XS GIS Cut Line= 4
        2819130.     10235322.04      2819661.92     10235121.32
      2820394.58     10234900.52       2820532.8     10234676.46
#Sta/Elev= 30
  3958.3 1039.99  4081.5 1034.02  4195.1 1029.84  4310.5  1027.3  4335.4 1025.76
  4833.6 1018.57  4969.4  1012.5  4979.9 1011.62  4986.8 1009.33  5000.8 1009.15
  5001.6 1006.93  5002.4 1006.43    5038 1006.93  5042.5 1013.51    5058 1017.12
  5063.4 1019.91  5073.9 1020.74  5096.2    1020  5129.2 1022.01  5200.4 1023.99
  5261.2 1028.23  5266.4 1027.74    5290 1030.28  5335.9 1030.11  5341.8 1031.08
  5357.2 1029.85  5378.5 1029.94  5473.1  1031.8  5552.3 1030.82  5555.3 1029.78
#Mann= 4 ,-1 , 0
  3958.3    .075       0  4081.5     .05       0  5001.6     .03       0
    5038     .05       0
Bank Sta=5001.6,5038
XS Rating Curve= 0 ,0
Exp/Cntr=0.3,0.1

Type RM Length L Ch R = 1 ,6697    ,697,697,697
BEGIN DESCRIPTION:
Mapping XS 92e13e6c
END DESCRIPTION:
XS GIS Cut Line= 4
      2818954.37     10235638.19      2819747.23     10235382.27
      2820319.31      10235171.5      2820575.25     10234850.32
#Sta/Elev= 30
  3732.9 1035.78  3928.6 1032.71  4343.8 1022.89  4355.6 1021.35  4542.6 1020.06
  4639.2 1021.48  4688.8 1020.86  4884.1 1018.78  4928.6 1016.51  4953.7 1009.02
  4983.1 1007.27    4984 1006.77  5019.5 1007.27  5022.7 1009.89  5039.8 1012.92
  5100.7 1017.93  5150.5 1027.38  5161.6 1031.94  5169.2 1031.28  5227.6 1030.43
  5342.3 1029.64  5350.4  1026.7  5356.7 1027.75  5364.8 1024.32  5378.2 1024.27
  5420.8 1025.97  5470.4 1024.58  5492.9 1029.16  5528.1 1030.18  5586.4 1029.59
#Mann= 7 ,-1 , 0
  3732.9     .05       0  4639.2     .12       0  4688.8     .05       0
  4983.1     .03       0  5019.5     .05       0  5169.2     .12       0
  5227.6     .05       0
Bank Sta=4983.1,5019.5
XS Rating Curve= 0 ,0
Exp/Cntr=0.3,0.1

Type RM Length L Ch R = 1 ,6000    ,500,500,500
BEGIN DESCRIPTION:
OATMAN CREEK 12.0
END DESCRIPTION:
XS GIS Cut Line= 3
      2819755.66     10236153.13        2820083.     10235899.18
      2821448.42     10235131.35
#Sta/Elev= 30
  4585.7 1029.18  4692.5 1024.46    4707  1022.8  4841.9 1021.48  4877.2 1016.47
  4964.1 1016.42  4966.7 1004.15  4967.5 1003.65  5003.2 1004.15  5005.5 1007.32
  5014.5 1006.05  5086.4 1009.73  5108.1 1010.93  5129.8  1013.7  5248.4 1015.66
  5329.3 1018.42  5345.3 1017.76  5394.3 1019.49  5534.6 1021.08  5556.3 1020.32
  5615.5 1014.51  5654.2 1012.17  5718.2 1014.38  5799.1 1014.05  5842.5 1016.76
  5913.9 1017.58  6115.9 1021.37  6306.6 1019.33  6387.5 1019.74  6566.5 1023.97
#Mann= 6 ,-1 , 0
  4585.7     .05       0  4966.7     .07       0  5003.2     .05       0
  5086.4     .05       0  5654.2     .12       0  5913.9     .05       0
Bank Sta=4966.7,5003.2
XS Rating Curve= 0 ,0
Exp/Cntr=0.3,0.1

Type RM Length L Ch R = 1 ,5500    ,500,500,500
BEGIN DESCRIPTION:
OATMAN CREEK 11.0
END DESCRIPTION:
XS GIS Cut Line= 3
      2819655.71     10236353.11      2820340.09     10236319.62
      2822105.65     10235953.12
#Sta/Elev= 30
  4314.8 1029.67    4475 1025.92  4620.9 1025.81  4795.4 1016.76  4905.5 1015.68
  4945.5  1010.7  4965.6 1005.16  4975.6 1004.39    4977 1002.83  4977.9 1002.33
  5013.5 1002.83  5029.7 1007.51  5046.6 1011.13  5108.3 1013.06  5240.6 1010.59
  5299.7 1013.01  5342.8 1016.83  5495.1 1019.24    5841 1009.62  6149.6 1009.12
  6231.3 1006.83  6251.7 1004.56  6337.2 1009.38  6619.4 1016.45  6639.8 1018.48
  6701.1 1029.23  6711.3 1032.65    6728 1034.87  6733.1  1037.8  6803.2 1042.27
#Mann= 5 ,-1 , 0
  4314.8     .05       0    4977     .03       0  5013.5     .05       0
  5029.7     .12       0  5108.3     .05       0
Bank Sta=4977,5013.5
XS Rating Curve= 0 ,0
Exp/Cntr=0.3,0.1

Type RM Length L Ch R = 1 ,5000    ,500,500,500
BEGIN DESCRIPTION:
OATMAN CREEK 10.0
END DESCRIPTION:
XS GIS Cut Line= 3
      2819755.66     10237403.13      2820731.43     10236618.02
      2821705.69     10236653.11
#Sta/Elev= 30
  3747.6 1033.77    3918 1025.73  3946.8 1022.37  3953.2 1024.05    4182 1013.46
  4409.1 1008.43  4415.5 1011.51  4423.5 1008.59  4429.9 1010.82  4458.7 1010.74
  4487.5 1005.43  4665.1 1011.42  4786.7 1011.64  4941.9 1003.58  4956.3  998.31
  4975.3  996.22  4999.4  997.37    5006   995.5  5006.9     995  5042.6   995.5
  5044.3  998.32  5124.3  999.48  5184.4 1007.92  5224.4 1006.03  5293.2 1008.43
  5394.5 1005.02  5444.5  999.55  5490.5 1003.34  5687.8  1010.6  5974.9 1021.12
#Mann= 7 ,-1 , 0
  3747.6     .05       0  4975.3     .12       0    5006     .07       0
  5042.6     .12       0  5293.2     .05       0  5490.5     .12       0
  5687.8     .05       0
Bank Sta=5006,5042.6
XS Rating Curve= 0 ,0
Exp/Cntr=0.3,0.1

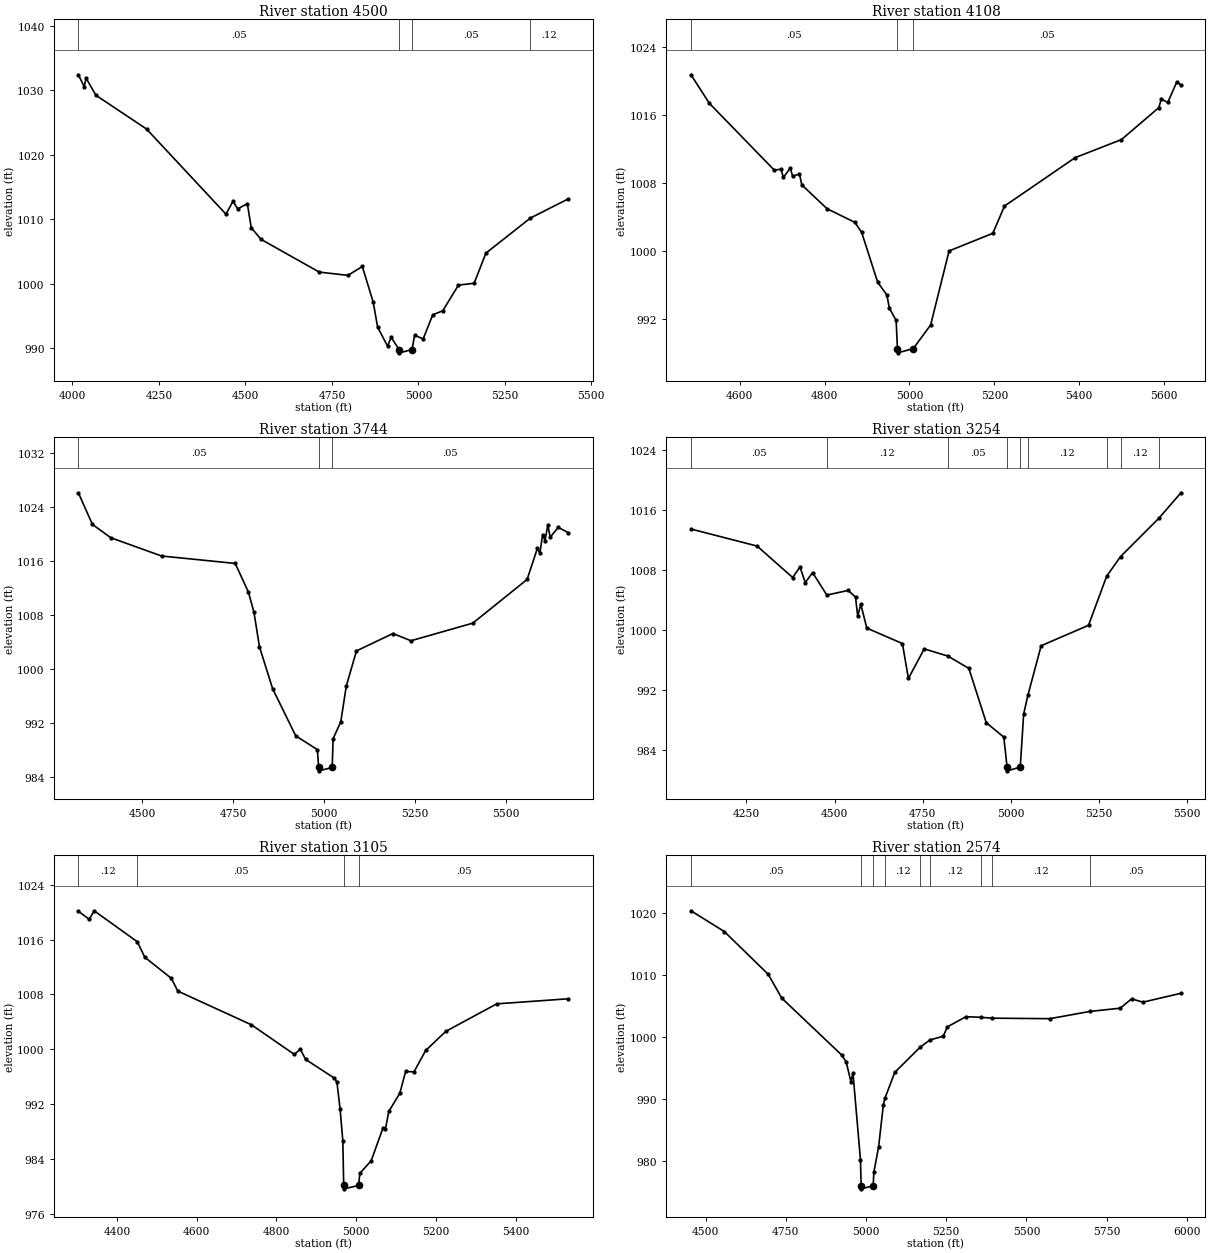
Type RM Length L Ch R = 1 ,4500    ,392,392,392
BEGIN DESCRIPTION:
OATMAN CREEK 9.0
END DESCRIPTION:
XS GIS Cut Line= 3
      2820705.68     10237953.13      2820973.54     10237007.43
      2821355.65     10236803.13
#Sta/Elev= 30
  4017.1 1032.39  4034.1 1030.54  4039.3 1031.88    4068 1029.21  4214.2 1023.98
  4443.8 1010.78    4464 1012.78  4477.7 1011.61  4505.6  1012.4  4516.8 1008.67
  4545.6 1006.86  4713.5  1001.8  4796.6 1001.29  4837.9 1002.67  4869.4  997.14
  4882.2  993.26  4910.9  990.32  4921.3  991.69  4944.4  989.78  4945.3  989.28
  4981.5  989.78  4989.2  992.02  5013.8  991.43  5041.5  995.18  5070.5   995.8
  5115.8  999.78  5161.2 1000.07  5195.2 1004.74  5323.9 1010.18  5433.3 1013.15
#Mann= 4 ,-1 , 0
  4017.1     .05       0  4944.4     .03       0  4981.5     .05       0
  5323.9     .12       0
Bank Sta=4944.4,4981.5
XS Rating Curve= 0 ,0
Exp/Cntr=0.3,0.1

Type RM Length L Ch R = 1 ,4108    ,364,364,364
BEGIN DESCRIPTION:
Mapping XS 3262fc35
END DESCRIPTION:
XS GIS Cut Line= 3
      2820916.47       10237781.      2821227.61     10237218.95
      2821659.18     10236942.94
#Sta/Elev= 30
    4485 1020.74  4528.3 1017.39  4681.1 1009.55  4697.1 1009.64  4702.8 1008.68
  4718.9 1009.78  4724.6 1008.82  4740.6  1009.1  4746.3  1007.8  4805.9    1005
  4871.2 1003.41  4887.2 1002.24    4925  996.37  4946.7  994.88  4952.4  993.35
  4968.5  991.88  4971.6  988.58  4972.5  988.08  5008.9  988.58  5049.8  991.35
  5093.3 1000.05  5196.4 1002.12  5223.9 1005.32  5390.5 1011.01  5499.6 1013.13
  5587.6 1016.88  5593.5 1017.89  5608.7 1017.49  5629.9 1019.89  5639.7 1019.54
#Mann= 3 ,-1 , 0
    4485     .05       0  4971.6     .03       0  5008.9     .05       0
Bank Sta=4971.6,5008.9
XS Rating Curve= 0 ,0
Exp/Cntr=0.3,0.1

Type RM Length L Ch R = 1 ,3744    ,490,490,490
BEGIN DESCRIPTION:
Mapping XS ecf6f0d2
END DESCRIPTION:
XS GIS Cut Line= 5
      2821067.05      10237926.5      2821237.65     10237836.19
      2821257.72     10237821.14      2821563.83     10237349.42
      2821935.18     10236922.87
#Sta/Elev= 30
  4324.9 1026.13  4363.6 1021.44  4413.9 1019.47  4553.5 1016.76  4755.9 1015.66
  4792.1 1011.41  4807.3 1008.44  4822.4 1003.32  4858.7  997.08  4922.1  990.11
  4981.7  988.06    4985  985.42    4986  984.92  5022.3  985.42  5024.8  989.68
  5045.9  992.19    5061  997.49    5089  1002.7  5189.3 1005.27  5238.6  1004.2
  5408.6 1006.81  5557.7 1013.28  5586.2 1017.92  5592.8 1017.16  5600.4 1019.91
    5607 1019.03  5614.6 1021.34  5621.3 1019.54  5643.1    1021  5670.9 1020.22
#Mann= 3 ,-1 , 0
  4324.9     .05       0    4985     .03       0  5022.3     .05       0
Bank Sta=4985,5022.3
XS Rating Curve= 0 ,0
Exp/Cntr=0.3,0.1

Type RM Length L Ch R = 1 ,3254    ,149,149,149
BEGIN DESCRIPTION:
Mapping XS c70b145e
END DESCRIPTION:
XS GIS Cut Line= 5
      2821237.66     10237996.76      2821624.05     10237720.77
      2821900.05     10237585.28      2822030.53     10237459.82
      2822326.62     10237153.69
#Sta/Elev= 30
    4093 1013.41  4280.5 1011.14  4381.3 1006.95  4402.2 1008.36  4416.9 1006.27
  4437.8  1007.6  4478.3 1004.61  4538.6 1005.23  4559.5 1004.34  4565.8 1001.78
  4574.5  1003.4  4591.5 1000.21  4692.5  998.15  4709.5   993.5  4754.4  997.44
  4821.5  996.48  4880.9  994.84  4930.3   987.6    4980  985.68  4989.3  981.69
  4990.2  981.19  5026.7  981.69  5036.3  988.77  5048.2  991.24  5085.9  997.86
  5220.2 1000.58  5271.7 1007.13  5310.9 1009.73  5420.4 1014.88  5482.2 1018.24
#Mann= 9 ,-1 , 0
    4093     .05       0  4478.3     .12       0  4821.5     .05       0
  4989.3     .03       0  5026.7     .05       0  5048.2     .12       0
  5271.7     .05       0  5310.9     .12       0  5420.4     .05       0
Bank Sta=4989.3,5026.7
XS Rating Curve= 0 ,0
Exp/Cntr=0.3,0.1

Type RM Length L Ch R = 1 ,3105    ,531,531,531
BEGIN DESCRIPTION:
Mapping XS d09ccd77
END DESCRIPTION:
XS GIS Cut Line= 4
      2821754.55     10238177.39      2821950.24     10237801.06
        2822161.       10237510.      2822521.49     10237249.65
#Sta/Elev= 30
  4303.3 1020.14  4330.7 1018.96  4342.9 1020.21  4451.1 1015.69  4469.9 1013.42
  4536.3 1010.35  4552.7 1008.48  4737.3 1003.56  4844.9  999.23  4859.6 1000.02
  4873.1   998.5  4945.4  995.76  4951.6  995.17  4959.5  991.25  4966.3   986.6
  4968.5  980.11  4969.4  979.61  5005.9  980.11  5008.9  981.87  5037.5  983.72
  5066.9  988.49    5073  988.31  5081.5  990.91  5109.1  993.56  5123.8  996.75
  5144.7  996.69  5174.1  999.82  5224.4  1002.6    5352 1006.62  5531.5 1007.36
#Mann= 4 ,-1 , 0
  4303.3     .12       0  4451.1     .05       0  4968.5     .03       0
  5005.9     .05       0
Bank Sta=4968.5,5005.9
XS Rating Curve= 0 ,0
Exp/Cntr=0.3,0.1

Type RM Length L Ch R = 1 ,2574    ,611,611,611
BEGIN DESCRIPTION:
Mapping XS 23ab349c
END DESCRIPTION:
XS GIS Cut Line= 3
      2821955.28       10238338.      2822637.74     10237851.25
      2823129.53     10237369.49
#Sta/Elev= 30
  4454.7 1020.36  4558.7 1017.01  4695.2 1010.14  4737.7 1006.28  4923.8  997.15
  4938.5     996  4953.3  992.77  4959.4  994.26  4982.8  980.27    4985  976.07
  4985.9  975.57  5022.4  976.07  5024.6  978.27  5039.3   982.3  5054.1  989.08
  5058.8  990.13  5089.7  994.33  5168.5  998.37  5199.1  999.55  5240.9 1000.15
  5253.6 1001.66  5311.4  1003.3    5358  1003.2  5394.2 1003.06    5573 1002.98
  5698.3 1004.15  5792.3 1004.67  5827.6 1006.17    5863 1005.64  5981.4 1007.07
#Mann= 9 ,-1 , 0
  4454.7     .05       0    4985     .05       0  5022.4     .05       0
  5058.8     .12       0  5168.5     .05       0  5199.1     .12       0
    5358     .05       0  5394.2     .12       0  5698.3     .05       0
Bank Sta=4985,5022.4
XS Rating Curve= 0 ,0
Exp/Cntr=0.3,0.1

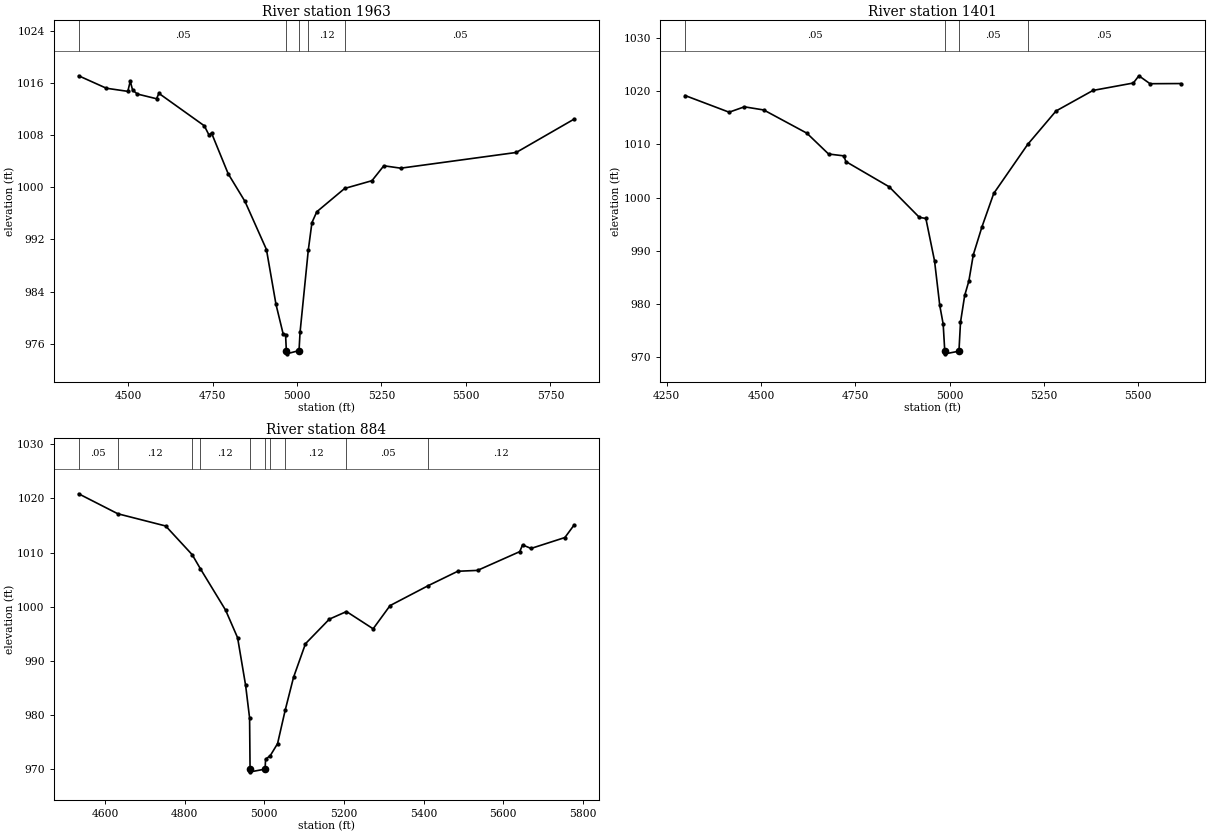
Type RM Length L Ch R = 1 ,1963    ,562,562,562
BEGIN DESCRIPTION:
Mapping XS de5a817b
END DESCRIPTION:
XS GIS Cut Line= 3
      2822331.64     10238925.13       2822793.3     10238478.53
      2823435.63     10237961.65
#Sta/Elev= 30
  4353.6 1017.09  4435.7 1015.18  4499.2  1014.7  4506.4 1016.26  4513.4 1014.89
  4527.5 1014.29  4584.1 1013.57  4591.3 1014.39  4725.6 1009.42  4739.7 1007.98
  4746.9 1008.32  4796.3 1002.06    4846  997.82  4909.5  990.45  4937.8  982.03
  4958.9  977.52  4966.1  977.41  4968.4  974.95  4969.4  974.45    5006  974.95
    5009  977.75  5033.4  990.36  5044.2  994.58  5058.6  996.24    5141  999.81
  5221.8    1001    5257 1003.29    5307 1002.92  5648.9 1005.33  5820.4 1010.45
#Mann= 5 ,-1 , 0
  4353.6     .05       0  4968.4     .05       0    5006     .05       0
  5033.4     .12       0    5141     .05       0
Bank Sta=4968.4,5006
XS Rating Curve= 0 ,0
Exp/Cntr=0.3,0.1

Type RM Length L Ch R = 1 ,1401    ,517,517,517
BEGIN DESCRIPTION:
Mapping XS fa8ec1d8
END DESCRIPTION:
XS GIS Cut Line= 3
      2822572.52     10239145.94      2823530.99     10238704.35
      2823741.25     10238554.16
#Sta/Elev= 30
    4299 1019.16  4415.7 1016.03  4456.1 1017.04  4507.5 1016.45  4621.8 1012.09
  4679.3 1008.18  4719.7 1007.83  4725.2 1006.76    4840 1002.02  4919.9  996.29
  4937.3  996.07  4960.3   988.1  4974.1  979.75  4983.2  976.23  4987.4  971.15
  4988.3  970.65    5025  971.15  5029.1  976.58  5040.2  981.61  5051.2  984.31
  5063.1  989.27  5086.1  994.52  5117.2 1000.77  5207.2 1009.98  5282.4 1016.26
  5380.4 1020.12  5487.3 1021.51    5502 1022.87  5531.5 1021.38  5612.7 1021.41
#Mann= 4 ,-1 , 0
    4299     .05       0  4987.4     .07       0    5025     .05       0
  5207.2     .05       0
Bank Sta=4987.4,5025
XS Rating Curve= 0 ,0
Exp/Cntr=0.3,0.1

Type RM Length L Ch R = 1 ,884     ,0,0,0
BEGIN DESCRIPTION:
Mapping XS 034f036f
END DESCRIPTION:
XS GIS Cut Line= 3
      2822637.69     10239261.37      2823270.04     10239306.54
      2823711.17     10238885.45
#Sta/Elev= 30
  4534.1 1020.83  4632.6 1017.14  4752.6 1014.89  4819.2 1009.59  4839.8 1006.99
    4903  999.37  4933.1  994.28  4953.2  985.51  4963.2  979.49  4964.4  970.05
  4965.4  969.55  5002.1  970.05  5003.3  971.86  5015.3  972.56  5033.4  974.75
  5052.5   980.9  5073.5  986.98  5103.5  993.18  5163.4  997.71  5206.4  999.11
  5273.3  995.93  5315.8 1000.21  5411.9  1003.9  5485.7 1006.54  5535.3  1006.7
  5641.3 1010.16  5648.3  1011.4  5669.7 1010.75  5754.6 1012.76  5777.9 1015.09
#Mann= 10 ,-1 , 0
  4534.1     .05       0  4632.6     .12       0  4819.2     .05       0
  4839.8     .12       0  4964.4     .07       0  5002.1     .12       0
  5015.3     .05       0  5052.5     .12       0  5206.4     .05       0
  5411.9     .12       0
Bank Sta=4964.4,5002.1
XS Rating Curve= 0 ,0
Exp/Cntr=0.3,0.1

Chan Stop Cuts=-1
Use User Specified Reach Order=0
Composite Channel Slope=5