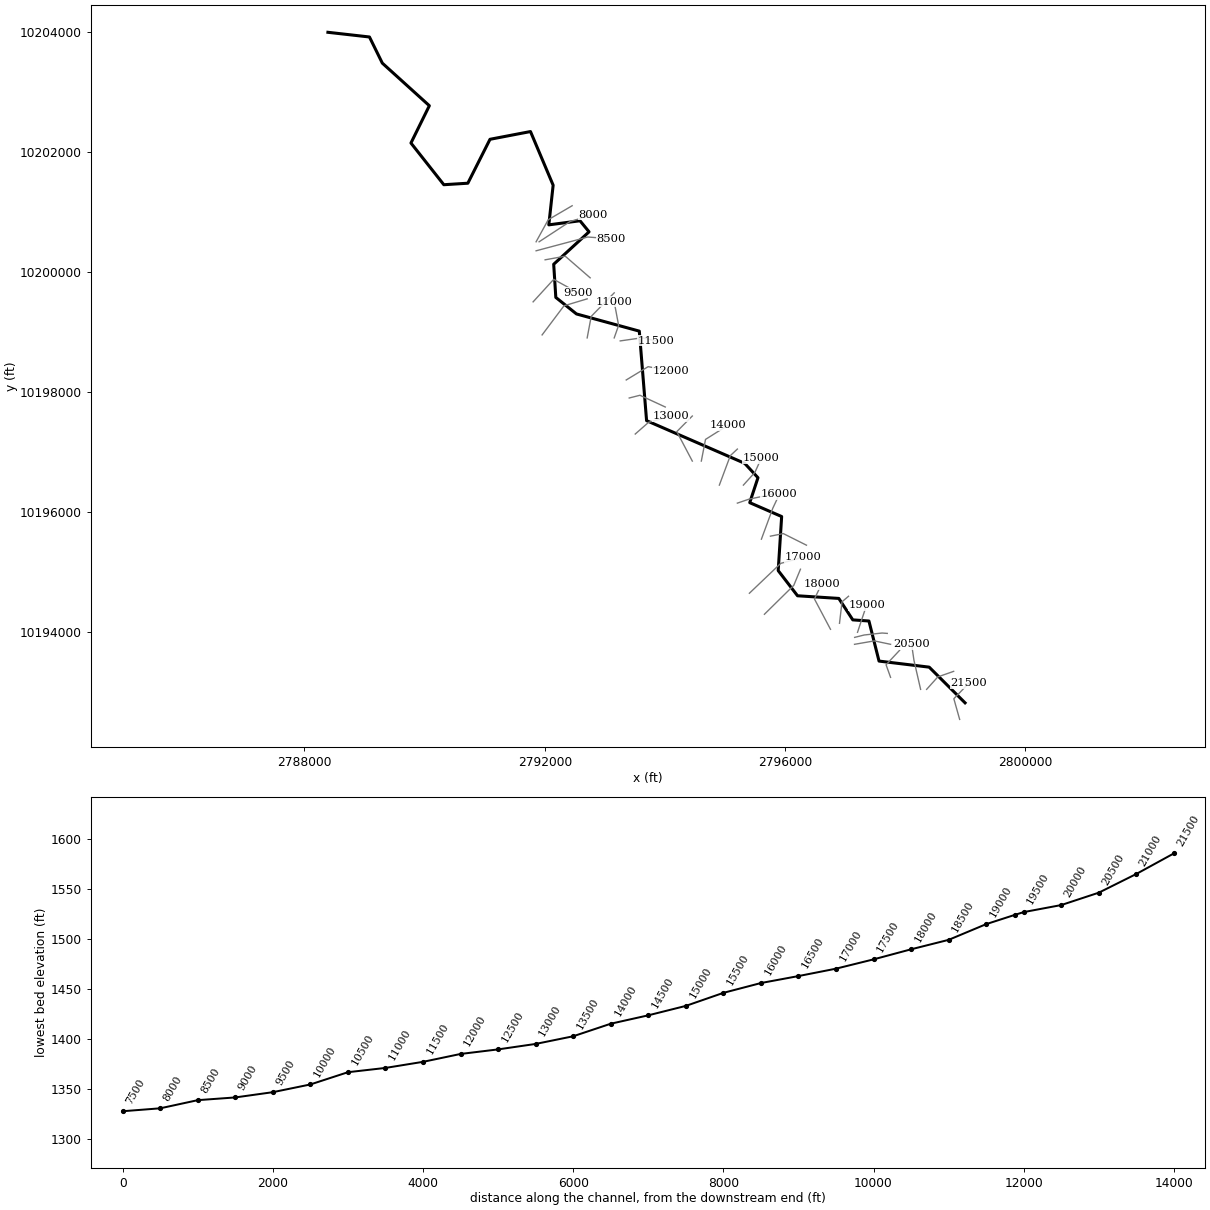
--- OWEN CREEK.prj (project) ---

Proj Title=OWEN CREEK Base Level Engineering
Current Plan=p01
Default Exp/Contr=0.3,0.1
English Units
Geom File=g01
Flow File=f01
Plan File=p01
BEGIN DESCRIPTION:
OWEN CREEK
END DESCRIPTION:

--- OWEN CREEK.p01 (plan) ---

Plan Title=Multiple Run
Short Identifier=Multiple
Geom File=g01
Flow File=f01
Subcritical Flow
K Sum by GR= 0
Std Step Tol= 0.01
Critical Tol= 0.01
Num of Std Step Trials= 20
Max Error Tol= 0.3
Flow Tol Ratio= 0.001
Split Flow NTrial= 30
Split Flow Tol= 0.02
Split Flow Ratio= 0.02
Log Output Level= 0
Friction Slope Method= 1
Unsteady Friction Slope Method= 2
Unsteady Bridges Friction Slope Method= 1
Parabolic Critical Depth
Global Vel Dist=  1 , 1 , 1
Global Log Level= 0
CheckData=True
Encroach Param= -1, 0, 0, 0
BEGIN DESCRIPTION:
Multiple Run
END DESCRIPTION:

--- OWEN CREEK.f01 (steady flow) ---

Flow Title=Multiple
Number of Profiles=7
Profile Names=10-year,25-year,50-year,1pct_min,100-year,1pct_plu,500-year
River Rch & RM= OWEN CREEK,Reach-1,21500
     405     648    1228     977    1697    2949    2422
River Rch & RM= OWEN CREEK,Reach-1,13500
     753    1264    2332    1451    3285    7440    4680
River Rch & RM= OWEN CREEK,Reach-1,6000
    1048    1788    3551    2602    5070    9879    7190
River Rch & RM= OWEN CREEK,Reach-1,4000
    1206    2084    3950    3345    5647    9533    7991
Boundary for River Rch & Prof#=OWEN CREEK,Reach-1,1
Up Type=0
Dn Type=3
Dn Slope=0.005
Boundary for River Rch & Prof#=OWEN CREEK,Reach-1,2
Up Type=0
Dn Type=3
Dn Slope=0.005
Boundary for River Rch & Prof#=OWEN CREEK,Reach-1,3
Up Type=0
Dn Type=3
Dn Slope=0.005
Boundary for River Rch & Prof#=OWEN CREEK,Reach-1,4
Up Type=0
Dn Type=3
Dn Slope=0.005
Boundary for River Rch & Prof#=OWEN CREEK,Reach-1,5
Up Type=0
Dn Type=3
Dn Slope=0.005
Boundary for River Rch & Prof#=OWEN CREEK,Reach-1,6
Up Type=0
Dn Type=3
Dn Slope=0.005
Boundary for River Rch & Prof#=OWEN CREEK,Reach-1,7
Up Type=0
Dn Type=3
Dn Slope=0.005

--- OWEN CREEK.g01 (geometry) ---

Geom Title=Existing Conditions

River Reach=OWEN CREEK,Reach-1
Reach XY= 30
      2798995.50     10192829.00      2798398.50     10193423.00
      2797563.50     10193524.00      2797395.50     10194191.00
      2797126.75     10194210.00      2796894.00     10194567.00
      2796207.00     10194611.00      2795885.25     10195030.00
      2795942.75     10195930.00      2795411.50     10196161.00
      2795548.50     10196576.00      2795326.75     10196816.00
      2793694.50     10197526.00      2793573.50     10199016.00
      2792527.50     10199302.00      2792183.75     10199577.00
      2792148.50     10200129.00      2792737.00     10200669.00
      2792586.25     10200853.00      2792067.25     10200785.00
      2792139.25     10201445.00      2791762.25     10202338.00
      2791088.25     10202209.00      2790719.50     10201478.00
      2790319.75     10201453.00      2789772.50     10202147.00
      2790078.75     10202768.00      2789295.75     10203477.00
      2789082.00     10203912.00      2788390.25     10203990.00

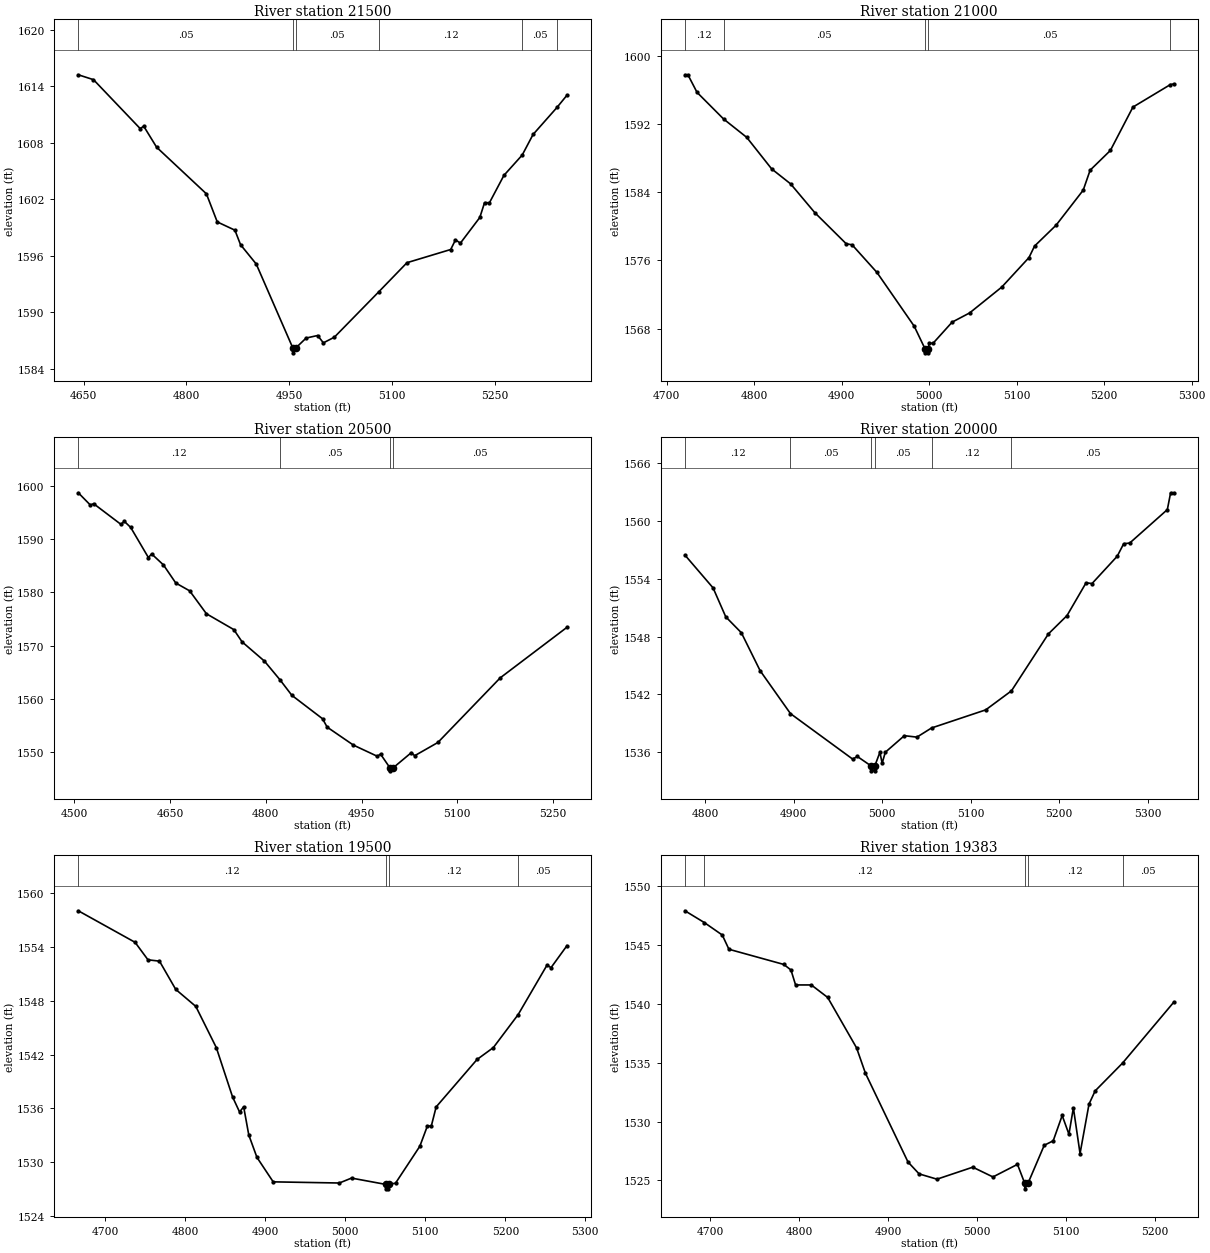
Type RM Length L Ch R = 1,21500,500,500,500
BEGIN DESCRIPTION:
OWEN CREEK 43.0
END DESCRIPTION:
XS GIS Cut Line= 3
      2798905.69     10192553.10      2798808.74     10192897.41
      2799055.70     10193153.13
#Sta/Elev= 30
  4642.3 1615.23  4664.5 1614.71  4732.6 1609.52  4737.8 1609.77  4756.6 1607.54
  4829.3 1602.59  4845.1 1599.61  4870.9 1598.73  4879.1 1597.19  4902.0 1595.14
  4955.5 1586.21  4955.8 1585.71  4959.5 1586.21  4974.8 1587.28  4991.6 1587.55
  5000.0 1586.77  5016.0 1587.37  5081.0 1592.20  5122.0 1595.28  5185.8 1596.68
  5192.8 1597.70  5200.0 1597.36  5228.3 1600.08  5235.2 1601.65  5242.4 1601.65
  5263.5 1604.55  5290.2 1606.71  5306.0 1608.89  5340.9 1611.76  5355.5 1613.06
#Mann=6,-1,0
  4642.3    0.05       0  4955.5    0.05       0  4959.5    0.05       0
  5081.0    0.12       0  5290.2    0.05       0  5340.9    0.12       0
Bank Sta=4955.5,4959.5
Exp/Cntr=0.3,0.1

Type RM Length L Ch R = 1,21000,500,500,500
BEGIN DESCRIPTION:
OWEN CREEK 42.0
END DESCRIPTION:
XS GIS Cut Line= 3
      2798355.68     10193053.10      2798541.99     10193260.78
      2798805.69     10193353.11
#Sta/Elev= 30
  4721.0 1597.77  4724.4 1597.77  4734.8 1595.71  4765.2 1592.58  4791.6 1590.43
  4820.1 1586.73  4841.7 1584.98  4869.4 1581.60  4905.3 1577.95  4912.0 1577.83
  4940.4 1574.59  4983.0 1568.28  4995.2 1565.66  4995.5 1565.16  4999.0 1565.16
  4999.2 1565.66  5000.0 1566.29  5004.6 1566.29  5026.3 1568.76  5046.3 1569.84
  5083.0 1572.87  5114.1 1576.33  5120.5 1577.68  5145.1 1580.13  5176.1 1584.24
  5184.0 1586.58  5207.1 1588.89  5232.9 1593.98  5275.7 1596.62  5279.4 1596.69
#Mann=5,-1,0
  4721.0    0.12       0  4765.2    0.05       0  4995.2    0.05       0
  4999.2    0.05       0  5275.7    0.12       0
Bank Sta=4995.2,4999.2
Exp/Cntr=0.3,0.1

Type RM Length L Ch R = 1,20500,500,500,500
BEGIN DESCRIPTION:
OWEN CREEK 41.0
END DESCRIPTION:
XS GIS Cut Line= 3
      2798255.68     10193053.13      2798145.35     10193534.34
      2798105.68     10193803.13
#Sta/Elev= 30
  4506.3 1598.74  4525.2 1596.43  4530.3 1596.69  4573.2 1592.79  4578.3 1593.38
  4588.4 1592.22  4616.1 1586.56  4621.2 1587.24  4639.7 1585.17  4659.0 1581.77
  4680.7 1580.30  4707.0 1575.99  4749.9 1573.01  4762.8 1570.71  4797.9 1567.08
  4822.4 1563.54  4840.8 1560.65  4888.8 1556.25  4896.1 1554.67  4937.2 1551.29
  4974.6 1549.19  4979.7 1549.60  4994.8 1546.95  4995.1 1546.45  4998.8 1546.95
  5028.0 1549.88  5033.1 1549.29  5069.5 1551.78  5167.2 1563.94  5271.7 1573.44
#Mann=4,-1,0
  4506.3    0.12       0  4822.4    0.05       0  4994.8    0.05       0
  4998.8    0.05       0
Bank Sta=4994.8,4998.8
Exp/Cntr=0.3,0.1

Type RM Length L Ch R = 1,20000,500,500,500
BEGIN DESCRIPTION:
OWEN CREEK 40.0
END DESCRIPTION:
XS GIS Cut Line= 3
      2797755.67     10193253.14      2797680.66     10193462.83
      2797905.68     10193703.11
#Sta/Elev= 30
  4777.3 1556.47  4809.1 1553.06  4823.4 1550.06  4841.0 1548.41  4862.2 1544.47
  4896.5 1540.01  4966.7 1535.29  4972.0 1535.56  4987.7 1534.57  4987.9 1534.07
  4991.4 1534.07  4991.7 1534.57  4997.5 1536.00  5000.0 1534.86  5003.6 1536.00
  5025.1 1537.72  5039.3 1537.57  5055.8 1538.52  5117.0 1540.40  5146.1 1542.38
  5187.8 1548.29  5208.8 1550.19  5230.3 1553.59  5237.1 1553.52  5265.5 1556.35
  5272.8 1557.65  5279.6 1557.72  5322.1 1561.19  5325.8 1562.94  5329.2 1562.94
#Mann=6,-1,0
  4777.3    0.12       0  4896.5    0.05       0  4987.7    0.05       0
  4991.7    0.05       0  5055.8    0.12       0  5146.1    0.05       0
Bank Sta=4987.7,4991.7
Exp/Cntr=0.3,0.1

Type RM Length L Ch R = 1,19500,117,117,117
BEGIN DESCRIPTION:
OWEN CREEK 39.0
END DESCRIPTION:
XS GIS Cut Line= 3
      2797155.69     10193803.11      2797484.61     10193860.00
      2797755.70     10193803.11
#Sta/Elev= 30
  4666.2 1558.04  4737.2 1554.52  4753.3 1552.57  4767.7 1552.42  4788.0 1549.27
  4813.1 1547.37  4838.7 1542.78  4859.0 1537.28  4867.8 1535.59  4872.9 1536.17
  4879.3 1533.03  4889.5 1530.53  4909.8 1527.80  4992.5 1527.67  5007.7 1528.22
  5050.2 1527.52  5050.4 1527.02  5053.9 1527.02  5054.2 1527.52  5062.7 1527.65
  5093.1 1531.77  5102.4 1534.00  5107.5 1534.05  5113.5 1536.16  5164.6 1541.45
  5185.0 1542.78  5216.0 1546.46  5252.0 1551.97  5257.1 1551.70  5277.0 1554.15
#Mann=4,-1,0
  4666.2    0.12       0  5050.2    0.07       0  5054.2    0.12       0
  5216.0    0.05       0
Bank Sta=5050.2,5054.2
Exp/Cntr=0.3,0.1

Type RM Length L Ch R = 1,19383,383,383,383
BEGIN DESCRIPTION:
Mapping XS f3b9cdc9
END DESCRIPTION:
XS GIS Cut Line= 4
      2797157.70     10193918.47      2797316.63     10193958.20
      2797614.57     10193991.31      2797700.62     10193984.69
#Sta/Elev= 30
  4671.3 1547.90  4693.3 1546.89  4713.3 1545.84  4720.8 1544.63  4782.6 1543.34
  4790.6 1542.87  4795.8 1541.60  4813.5 1541.60  4831.9 1540.54  4864.4 1536.26
  4874.4 1534.10  4922.3 1526.56  4934.8 1525.55  4954.9 1525.10  4995.2 1526.12
  5017.9 1525.29  5045.5 1526.36  5053.5 1524.78  5053.8 1524.28  5057.5 1524.78
  5075.6 1527.98  5085.7 1528.36  5095.8 1530.51  5103.4 1528.92  5108.4 1531.16
  5115.9 1527.28  5126.0 1531.48  5132.9 1532.60  5163.7 1534.96  5221.2 1540.12
#Mann=5,-1,0
  4671.3    0.05       0  4693.3    0.12       0  5053.5    0.07       0
  5057.5    0.12       0  5163.7    0.05       0
Bank Sta=5053.5,5057.5
Exp/Cntr=0.3,0.1

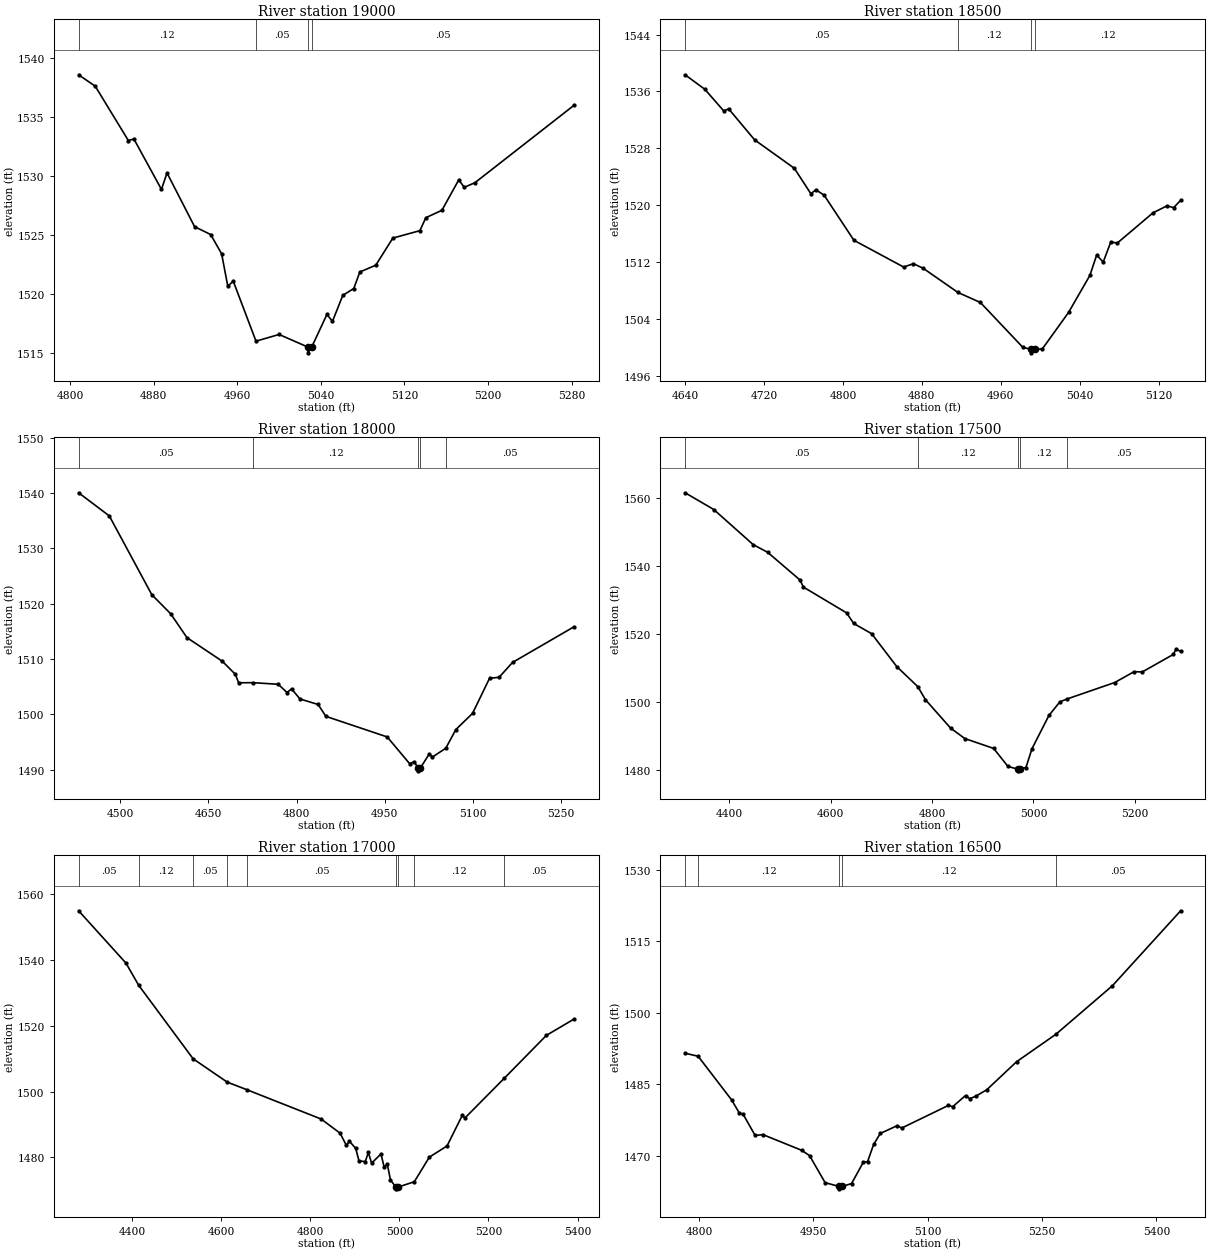
Type RM Length L Ch R = 1,19000,500,500,500
BEGIN DESCRIPTION:
OWEN CREEK 38.0
END DESCRIPTION:
XS GIS Cut Line= 3
      2797205.68     10194003.10      2797265.93     10194185.30
      2797355.70     10194453.16
#Sta/Elev= 30
  4808.1 1538.58  4824.0 1537.61  4855.7 1533.00  4861.0 1533.13  4887.4 1528.85
  4892.7 1530.25  4919.1 1525.69  4934.5 1525.02  4945.0 1523.39  4950.9 1520.63
  4956.1 1521.07  4977.9 1515.97  5000.0 1516.54  5027.3 1515.48  5027.6 1514.98
  5031.3 1515.48  5045.8 1518.24  5051.1 1517.65  5061.0 1519.86  5071.5 1520.44
  5077.3 1521.84  5092.6 1522.42  5108.9 1524.72  5134.8 1525.35  5140.5 1526.45
  5155.9 1527.08  5172.0 1529.66  5177.3 1529.03  5187.5 1529.42  5282.5 1536.00
#Mann=4,-1,0
  4808.1    0.12       0  4977.9    0.05       0  5027.3    0.05       0
  5031.3    0.05       0
Bank Sta=5027.3,5031.3
Exp/Cntr=0.3,0.1

Type RM Length L Ch R = 1,18500,500,500,500
BEGIN DESCRIPTION:
OWEN CREEK 37.0
END DESCRIPTION:
XS GIS Cut Line= 3
      2796905.69     10194153.13      2796947.46     10194510.70
      2797055.68     10194603.11
#Sta/Elev= 30
  4640.0 1538.35  4660.1 1536.30  4679.1 1533.28  4684.2 1533.55  4710.5 1529.20
  4750.7 1525.21  4767.5 1521.63  4772.6 1522.19  4780.9 1521.43  4811.1 1515.09
  4861.5 1511.33  4871.5 1511.80  4881.6 1511.13  4916.5 1507.76  4939.3 1506.35
  4982.3 1500.05  4990.4 1499.77  4990.6 1499.27  4994.4 1499.77  5002.1 1499.82
  5028.7 1504.95  5050.3 1510.15  5057.2 1513.02  5063.8 1512.02  5071.5 1514.85
  5078.1 1514.70  5114.3 1518.95  5128.6 1519.94  5135.2 1519.67  5142.3 1520.71
#Mann=4,-1,0
  4640.0    0.05       0  4916.5    0.12       0  4990.4    0.07       0
  4994.4    0.12       0
Bank Sta=4990.4,4994.4
Exp/Cntr=0.3,0.1

Type RM Length L Ch R = 1,18000,500,500,500
BEGIN DESCRIPTION:
OWEN CREEK 36.0
END DESCRIPTION:
XS GIS Cut Line= 3
      2796755.70     10194053.08      2796488.54     10194557.62
      2796605.68     10194803.10
#Sta/Elev= 30
  4429.1 1540.03  4481.3 1535.85  4553.6 1521.62  4585.6 1518.19  4613.3 1513.88
  4673.6 1509.60  4695.6 1507.26  4701.3 1505.72  4726.2 1505.74  4768.6 1505.45
  4783.6 1503.96  4791.2 1504.63  4805.6 1502.80  4836.5 1501.80  4849.6 1499.66
  4954.0 1495.94  4992.3 1491.09  5000.0 1491.49  5006.3 1490.32  5006.6 1489.82
  5010.3 1490.32  5025.5 1492.87  5031.0 1492.32  5053.6 1493.90  5070.8 1497.28
  5099.1 1500.19  5128.0 1506.52  5144.4 1506.72  5167.1 1509.39  5272.0 1515.85
#Mann=5,-1,0
  4429.1    0.05       0  4726.2    0.12       0  5006.3    0.07       0
  5010.3    0.12       0  5053.6    0.05       0
Bank Sta=5006.3,5010.3
Exp/Cntr=0.3,0.1

Type RM Length L Ch R = 1,17500,500,500,500
BEGIN DESCRIPTION:
OWEN CREEK 35.0
END DESCRIPTION:
XS GIS Cut Line= 3
      2795655.72     10194303.15      2796144.88     10194784.95
      2796255.67     10195053.07
#Sta/Elev= 30
  4313.4 1561.56  4369.9 1556.64  4447.7 1546.30  4476.0 1544.06  4539.6 1535.93
  4546.7 1533.80  4631.6 1526.24  4645.7 1523.11  4681.0 1520.11  4730.6 1510.42
  4772.0 1504.53  4787.2 1500.67  4836.6 1492.33  4864.9 1489.24  4921.5 1486.35
  4949.7 1481.05  4969.0 1480.25  4969.3 1479.75  4973.0 1480.25  4985.2 1480.73
  4997.1 1486.26  5030.5 1496.05  5052.1 1500.05  5066.5 1500.91  5160.3 1505.74
  5198.3 1508.92  5214.4 1508.84  5275.5 1513.99  5280.9 1515.50  5290.1 1514.93
#Mann=5,-1,0
  4313.4    0.05       0  4772.0    0.12       0  4969.0    0.07       0
  4973.0    0.12       0  5066.5    0.05       0
Bank Sta=4969,4973
Exp/Cntr=0.3,0.1

Type RM Length L Ch R = 1,17000,500,500,500
BEGIN DESCRIPTION:
OWEN CREEK 34.0
END DESCRIPTION:
XS GIS Cut Line= 3
      2795405.65     10194653.08      2795927.00     10195150.24
      2796305.68     10195253.11
#Sta/Elev= 30
  4279.6 1554.86  4385.8 1538.99  4414.4 1532.26  4536.7 1509.93  4613.3 1502.85
  4658.1 1500.51  4824.2 1491.65  4866.7 1487.36  4880.9 1483.64  4887.8 1484.90
  4901.9 1482.71  4909.2 1478.92  4923.3 1478.74  4930.2 1481.50  4937.5 1478.25
  4958.5 1481.04  4965.8 1477.01  4972.7 1477.99  4979.9 1473.16  4992.1 1470.96
  4992.3 1470.46  4996.1 1470.96  5033.4 1472.61  5067.1 1480.07  5106.9 1483.48
  5141.5 1492.86  5146.7 1491.91  5235.7 1504.06  5330.1 1517.05  5392.4 1522.02
#Mann=9,-1,0
  4279.6    0.05       0  4414.4    0.12       0  4536.7    0.05       0
  4613.3    0.12       0  4658.1    0.05       0  4992.1    0.03       0
  4996.1    0.05       0  5033.4    0.12       0  5235.7    0.05       0
Bank Sta=4992.1,4996.1
Exp/Cntr=0.3,0.1

Type RM Length L Ch R = 1,16500,500,500,500
BEGIN DESCRIPTION:
OWEN CREEK 33.0
END DESCRIPTION:
XS GIS Cut Line= 3
      2795755.65     10195603.10      2795969.72     10195646.39
      2796355.72     10195453.09
#Sta/Elev= 30
  4781.6 1491.50  4798.7 1490.86  4842.8 1481.67  4852.6 1478.99  4857.7 1478.71
  4873.5 1474.25  4883.7 1474.43  4934.7 1471.13  4944.9 1470.02  4965.3 1464.35
  4983.7 1463.56  4983.9 1463.06  4987.7 1463.56  5000.0 1464.17  5015.4 1468.65
  5021.0 1468.77  5029.0 1472.39  5037.7 1474.67  5060.1 1476.33  5065.7 1475.80
  5127.1 1480.56  5132.7 1480.29  5149.5 1482.63  5155.1 1481.96  5163.2 1482.51
  5177.4 1483.84  5216.5 1489.72  5268.1 1495.48  5342.2 1505.65  5431.7 1521.37
#Mann=5,-1,0
  4781.6    0.05       0  4798.7    0.12       0  4983.7    0.07       0
  4987.7    0.12       0  5268.1    0.05       0
Bank Sta=4983.7,4987.7
Exp/Cntr=0.3,0.1

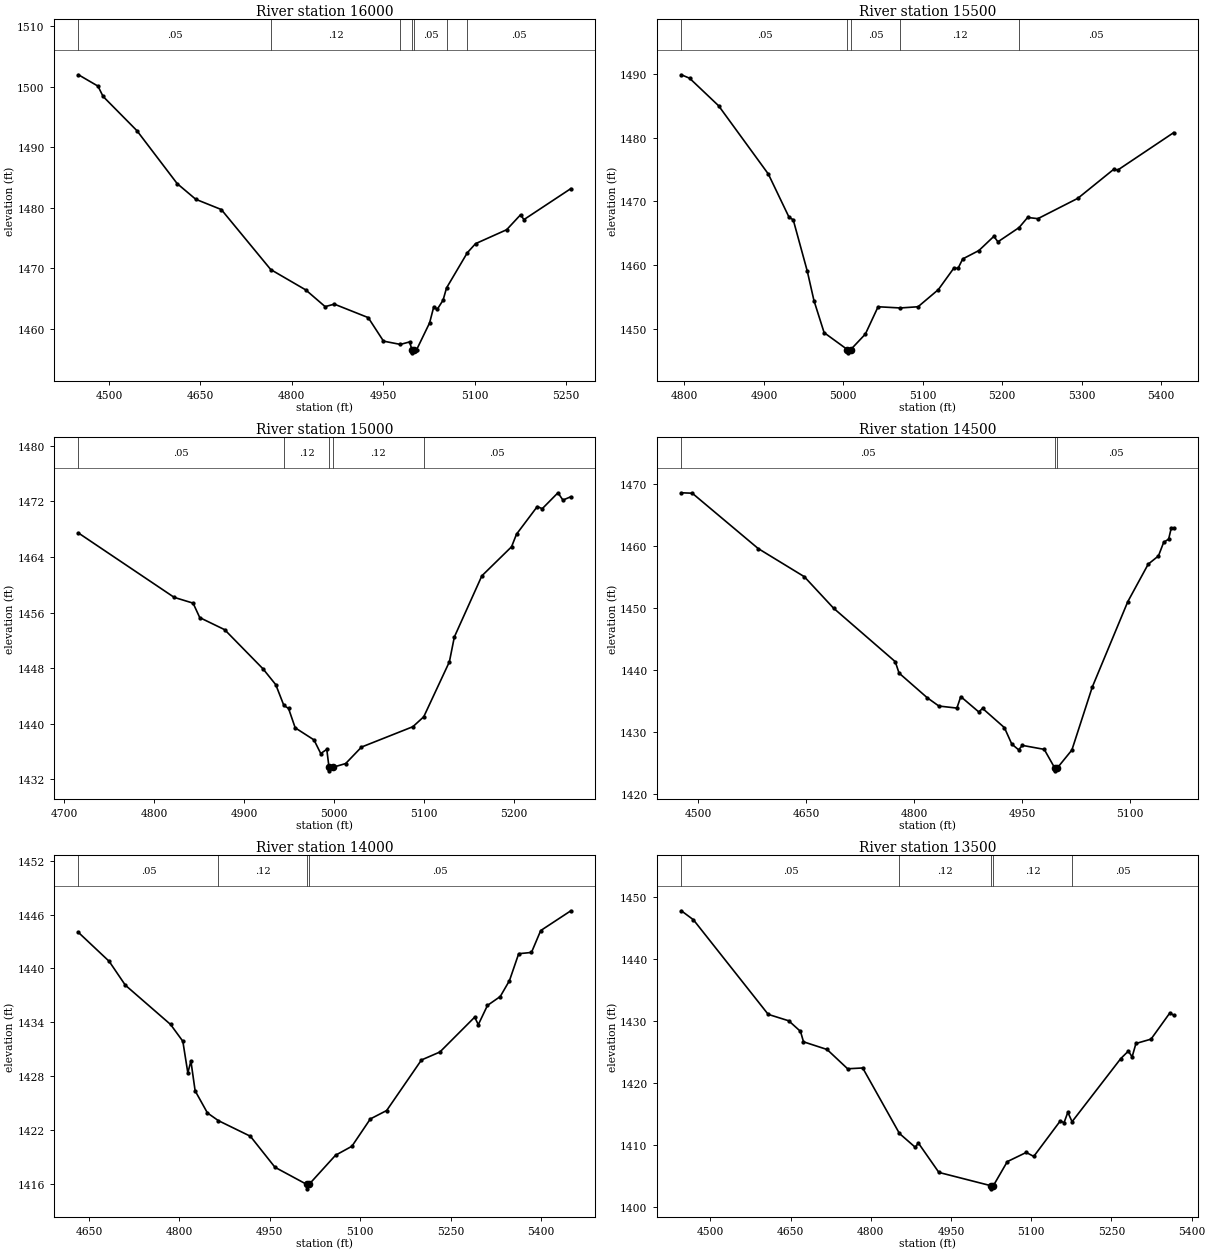
Type RM Length L Ch R = 1,16000,500,500,500
BEGIN DESCRIPTION:
OWEN CREEK 32.0
END DESCRIPTION:
XS GIS Cut Line= 3
      2795605.67     10195553.08      2795796.03     10196069.41
      2795905.66     10196303.07
#Sta/Elev= 30
  4449.7 1501.94  4481.7 1500.07  4490.1 1498.37  4545.6 1492.73  4611.8 1483.99
  4642.3 1481.41  4684.2 1479.72  4765.4 1469.82  4822.8 1466.47  4854.7 1463.71
  4869.8 1464.12  4925.4 1461.90  4950.5 1458.02  4978.2 1457.48  4993.3 1457.89
  4997.3 1456.59  4997.6 1456.09  5001.3 1456.59  5004.8 1456.59  5026.2 1461.03
  5033.1 1463.71  5038.6 1463.24  5048.3 1464.77  5054.0 1466.79  5088.1 1472.59
  5101.6 1474.09  5152.7 1476.39  5175.5 1478.85  5181.1 1478.06  5258.1 1483.17
#Mann=7,-1,0
  4449.7    0.05       0  4765.4    0.12       0  4978.2    0.05       0
  4997.3    0.05       0  5001.3    0.05       0  5054.0    0.12       0
  5088.1    0.05       0
Bank Sta=4997.3,5001.3
Exp/Cntr=0.3,0.1

Type RM Length L Ch R = 1,15500,500,500,500
BEGIN DESCRIPTION:
OWEN CREEK 31.0
END DESCRIPTION:
XS GIS Cut Line= 3
      2795205.68     10196153.11      2795398.60     10196219.12
      2795805.73     10196303.12
#Sta/Elev= 30
  4796.1 1489.83  4806.5 1489.29  4843.0 1484.98  4905.6 1474.28  4931.7 1467.50
  4936.9 1467.12  4954.6 1459.07  4963.0 1454.46  4975.8 1449.43  5005.2 1446.77
  5005.5 1446.27  5009.2 1446.77  5027.7 1449.21  5043.7 1453.49  5071.6 1453.30
  5094.0 1453.49  5119.5 1456.17  5139.2 1459.57  5144.3 1459.50  5150.2 1460.98
  5170.6 1462.30  5189.4 1464.52  5194.5 1463.66  5221.1 1465.89  5231.9 1467.48
  5244.8 1467.29  5295.1 1470.48  5340.2 1475.02  5345.4 1474.91  5415.7 1480.77
#Mann=5,-1,0
  4796.1    0.05       0  5005.2    0.05       0  5009.2    0.05       0
  5071.6    0.12       0  5221.1    0.05       0
Bank Sta=5005.2,5009.2
Exp/Cntr=0.3,0.1

Type RM Length L Ch R = 1,15000,500,500,500
BEGIN DESCRIPTION:
OWEN CREEK 30.0
END DESCRIPTION:
XS GIS Cut Line= 3
      2795305.71     10196453.14      2795496.65     10196663.77
      2795605.68     10196903.10
#Sta/Elev= 30
  4715.7 1467.45  4822.1 1458.19  4843.1 1457.36  4850.5 1455.28  4878.2 1453.54
  4920.8 1447.91  4935.0 1445.63  4944.0 1442.64  4949.2 1442.21  4956.6 1439.42
  4977.5 1437.68  4985.0 1435.72  4991.7 1436.32  4994.2 1433.73  4994.4 1433.23
  4998.2 1433.73  5012.7 1434.28  5030.3 1436.65  5087.4 1439.58  5099.5 1441.01
  5128.0 1448.92  5133.5 1452.49  5164.1 1461.29  5197.1 1465.47  5202.6 1467.28
  5225.7 1471.26  5231.2 1470.95  5248.7 1473.24  5254.2 1472.19  5263.0 1472.67
#Mann=5,-1,0
  4715.7    0.05       0  4944.0    0.12       0  4994.2    0.07       0
  4998.2    0.12       0  5099.5    0.05       0
Bank Sta=4994.2,4998.2
Exp/Cntr=0.3,0.1

Type RM Length L Ch R = 1,14500,500,500,500
BEGIN DESCRIPTION:
OWEN CREEK 29.0
END DESCRIPTION:
XS GIS Cut Line= 3
      2794905.68     10196453.11      2795088.38     10196943.37
      2795205.66     10197053.09
#Sta/Elev= 30
  4476.8 1468.61  4492.0 1468.54  4583.5 1459.63  4647.6 1455.09  4688.2 1450.02
  4773.9 1441.40  4779.2 1439.56  4818.3 1435.59  4834.5 1434.25  4859.5 1433.92
  4864.9 1435.77  4889.9 1433.30  4895.2 1433.87  4925.5 1430.77  4935.7 1428.13
  4945.2 1427.20  4950.5 1427.91  4980.8 1427.27  4995.2 1424.31  4995.4 1423.81
  4999.2 1424.31  5019.2 1427.16  5047.5 1437.30  5096.9 1451.08  5125.2 1457.11
  5139.4 1458.43  5146.7 1460.63  5153.6 1461.15  5157.2 1462.92  5160.6 1462.92
#Mann=3,-1,0
  4476.8    0.05       0  4995.2    0.05       0  4999.2    0.05       0
Bank Sta=4995.2,4999.2
Exp/Cntr=0.3,0.1

Type RM Length L Ch R = 1,14000,500,500,500
BEGIN DESCRIPTION:
OWEN CREEK 28.0
END DESCRIPTION:
XS GIS Cut Line= 3
      2794605.69     10196853.12      2794675.35     10197213.85
      2795055.65     10197453.09
#Sta/Elev= 30
  4632.6 1444.02  4683.5 1440.80  4710.3 1438.14  4785.4 1433.75  4805.7 1431.88
  4814.0 1428.35  4819.1 1429.67  4826.1 1426.35  4846.5 1423.88  4864.7 1423.02
  4917.7 1421.28  4958.5 1417.82  5011.1 1415.91  5011.3 1415.41  5015.1 1415.91
  5059.0 1419.16  5086.1 1420.16  5116.7 1423.21  5143.8 1424.15  5201.5 1429.79
  5232.1 1430.68  5289.8 1434.57  5295.8 1433.73  5311.0 1435.88  5332.2 1436.87
  5347.5 1438.65  5362.8 1441.65  5384.0 1441.79  5399.3 1444.23  5449.3 1446.44
#Mann=4,-1,0
  4632.6    0.05       0  4864.7    0.12       0  5011.1    0.07       0
  5015.1    0.05       0
Bank Sta=5011.1,5015.1
Exp/Cntr=0.3,0.1

Type RM Length L Ch R = 1,13500,500,500,500
BEGIN DESCRIPTION:
OWEN CREEK 27.0
END DESCRIPTION:
XS GIS Cut Line= 3
      2794455.67     10196853.13      2794197.29     10197343.41
      2794455.65     10197603.08
#Sta/Elev= 30
  4445.8 1447.73  4468.4 1446.28  4608.2 1431.02  4646.6 1429.98  4668.6 1428.27
  4674.2 1426.59  4718.3 1425.35  4756.7 1422.24  4784.9 1422.37  4853.6 1411.80
  4883.2 1409.57  4888.9 1410.27  4927.3 1405.52  5024.8 1403.37  5025.1 1402.87
  5029.1 1403.37  5055.2 1407.26  5090.6 1408.74  5104.7 1408.10  5154.2 1413.82
  5161.3 1413.54  5168.4 1415.22  5176.3 1413.70  5267.4 1423.89  5281.5 1425.09
  5288.6 1424.16  5295.7 1426.32  5323.9 1427.02  5359.3 1431.27  5366.3 1430.86
#Mann=5,-1,0
  4445.8    0.05       0  4853.6    0.12       0  5024.8    0.07       0
  5029.1    0.12       0  5176.3    0.05       0
Bank Sta=5024.8,5029.1
Exp/Cntr=0.3,0.1

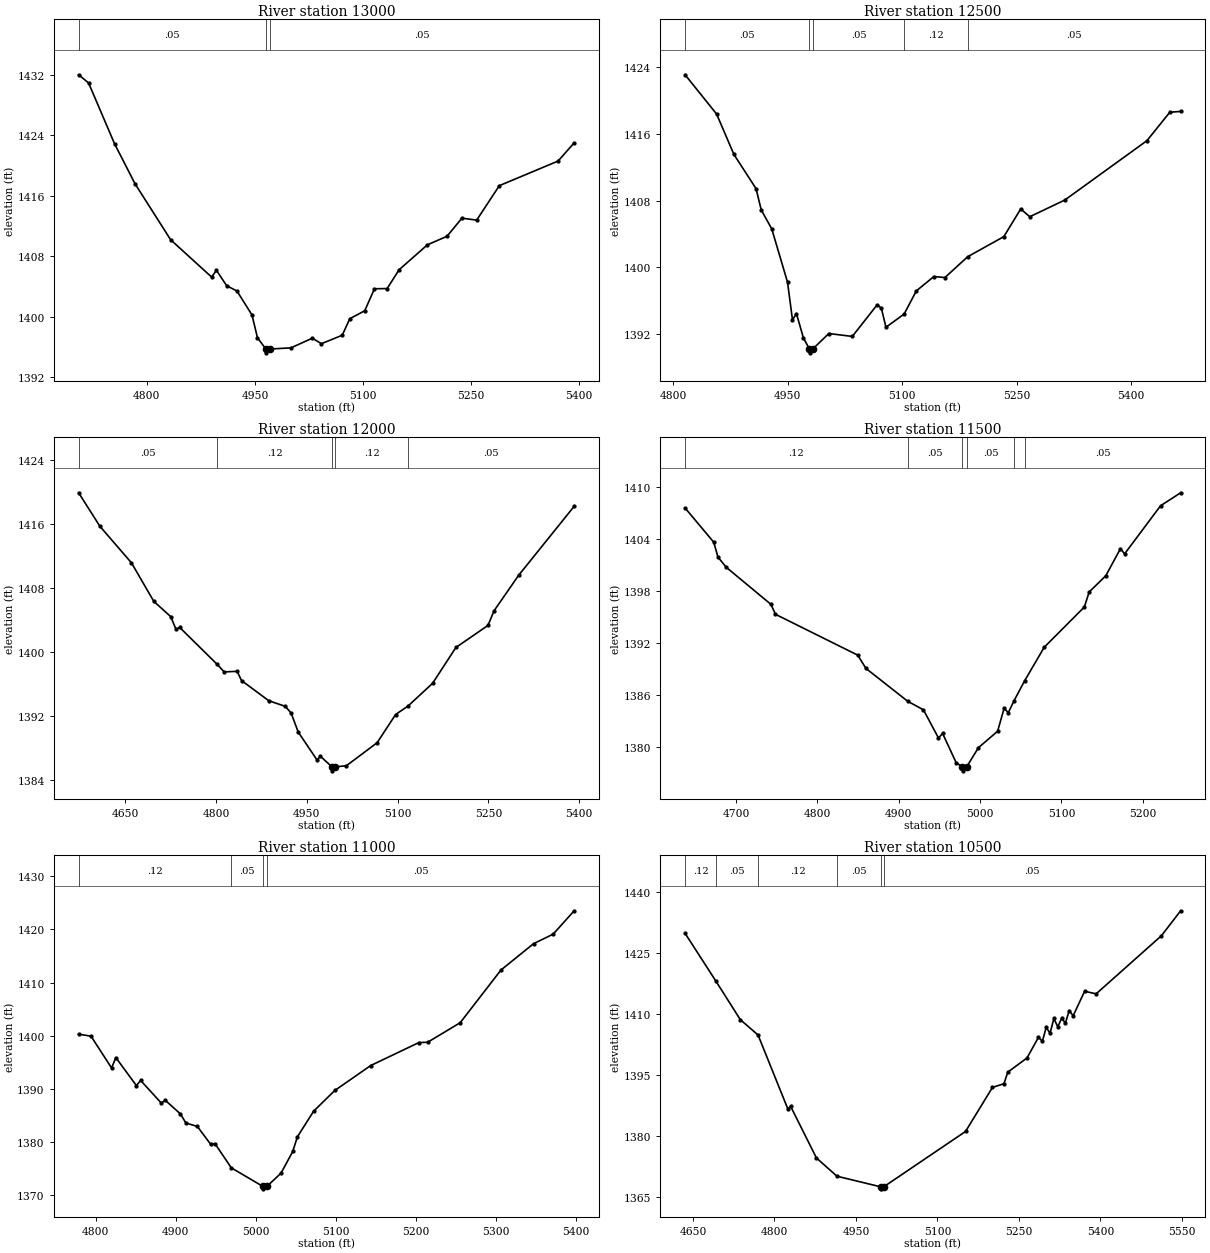
Type RM Length L Ch R = 1,13000,500,500,500
BEGIN DESCRIPTION:
OWEN CREEK 26.0
END DESCRIPTION:
XS GIS Cut Line= 3
      2793505.65     10197303.08      2793727.07     10197497.55
      2794105.73     10197603.12
#Sta/Elev= 30
  4705.3 1432.01  4719.1 1430.93  4755.2 1422.87  4783.6 1417.58  4833.0 1410.17
  4889.9 1405.23  4896.6 1406.13  4910.8 1404.08  4925.0 1403.39  4945.9 1400.22
  4953.5 1397.20  4965.2 1395.70  4965.6 1395.20  4970.3 1395.70  5000.0 1395.86
  5029.7 1397.14  5042.3 1396.41  5071.2 1397.53  5081.7 1399.72  5102.4 1400.77
  5115.9 1403.68  5133.5 1403.71  5150.1 1406.20  5189.4 1409.50  5216.6 1410.63
  5237.3 1413.03  5257.8 1412.77  5289.2 1417.33  5370.8 1420.59  5393.1 1423.00
#Mann=3,-1,0
  4705.3    0.05       0  4965.2    0.05       0  4970.3    0.05       0
Bank Sta=4965.2,4970.3
Exp/Cntr=0.3,0.1

Type RM Length L Ch R = 1,12500,500,500,500
BEGIN DESCRIPTION:
OWEN CREEK 25.0
END DESCRIPTION:
XS GIS Cut Line= 3
      2793405.68     10197903.11      2793584.10     10197948.51
      2794005.71     10197753.10
#Sta/Elev= 30
  4815.9 1423.12  4857.2 1418.40  4879.8 1413.56  4908.8 1409.45  4915.6 1406.89
  4929.4 1404.61  4950.0 1398.22  4956.5 1393.70  4961.7 1394.45  4970.7 1391.56
  4978.4 1390.24  4978.8 1389.74  4983.5 1390.24  5004.1 1392.06  5034.8 1391.71
  5067.3 1395.50  5072.8 1395.12  5078.9 1392.81  5102.7 1394.40  5118.7 1397.18
  5141.6 1398.90  5156.1 1398.78  5185.9 1401.28  5233.2 1403.69  5255.3 1407.01
  5267.2 1406.08  5313.0 1408.08  5420.6 1415.21  5450.5 1418.62  5464.7 1418.72
#Mann=5,-1,0
  4815.9    0.05       0  4978.4    0.05       0  4983.5    0.05       0
  5102.7    0.12       0  5185.9    0.05       0
Bank Sta=4978.4,4983.5
Exp/Cntr=0.3,0.1

Type RM Length L Ch R = 1,12000,500,500,500
BEGIN DESCRIPTION:
OWEN CREEK 24.0
END DESCRIPTION:
XS GIS Cut Line= 3
      2793355.66     10198203.09      2793720.50     10198424.37
      2794105.67     10198353.12
#Sta/Elev= 30
  4573.3 1419.89  4608.4 1415.71  4660.6 1411.14  4697.4 1406.34  4725.4 1404.43
  4734.2 1402.83  4740.1 1403.09  4802.0 1398.48  4813.7 1397.53  4835.1 1397.60
  4842.3 1396.45  4887.4 1393.93  4914.6 1393.23  4924.2 1392.40  4935.9 1390.03
  4966.9 1386.55  4972.7 1386.99  4991.7 1385.68  4992.1 1385.18  4996.9 1385.68
  5015.4 1385.81  5066.3 1388.69  5096.8 1392.21  5117.3 1393.27  5157.8 1396.10
  5196.4 1400.58  5249.3 1403.33  5259.5 1405.17  5300.2 1409.61  5391.7 1418.20
#Mann=5,-1,0
  4573.3    0.05       0  4802.0    0.12       0  4991.7    0.07       0
  4996.9    0.12       0  5117.3    0.05       0
Bank Sta=4991.7,4996.9
Exp/Cntr=0.3,0.1

Type RM Length L Ch R = 1,11500,500,500,500
BEGIN DESCRIPTION:
OWEN CREEK 23.0
END DESCRIPTION:
XS GIS Cut Line= 3
      2793255.69     10198853.11      2793614.57     10198904.93
      2793855.66     10198853.12
#Sta/Elev= 30
  4637.4 1407.62  4672.6 1403.68  4677.8 1401.96  4687.9 1400.79  4742.9 1396.51
  4748.5 1395.36  4849.6 1390.65  4859.7 1389.12  4911.0 1385.33  4930.4 1384.34
  4948.9 1381.09  4954.0 1381.61  4970.8 1378.21  4978.1 1377.80  4978.5 1377.30
  4983.8 1377.80  4998.0 1379.97  5021.6 1381.87  5029.6 1384.53  5034.7 1384.00
  5041.8 1385.39  5054.7 1387.67  5078.9 1391.56  5128.3 1396.21  5134.1 1397.93
  5154.6 1399.81  5172.6 1402.93  5177.7 1402.33  5221.9 1407.88  5246.6 1409.38
#Mann=6,-1,0
  4637.4    0.12       0  4911.0    0.05       0  4978.1    0.05       0
  4983.8    0.05       0  5041.8    0.12       0  5054.7    0.05       0
Bank Sta=4978.1,4983.8
Exp/Cntr=0.3,0.1

Type RM Length L Ch R = 1,11000,500,500,500
BEGIN DESCRIPTION:
OWEN CREEK 22.0
END DESCRIPTION:
XS GIS Cut Line= 3
      2793155.69     10198903.12      2793229.07     10199112.01
      2793155.69     10199503.09
#Sta/Elev= 30
  4778.6 1400.29  4794.1 1399.91  4819.8 1393.93  4825.1 1395.89  4850.8 1390.62
  4856.1 1391.59  4881.7 1387.37  4887.0 1387.84  4905.8 1385.30  4912.7 1383.58
  4927.0 1382.94  4943.7 1379.57  4949.0 1379.71  4969.4 1375.16  5008.4 1371.71
  5008.8 1371.21  5014.2 1371.71  5031.6 1374.17  5046.2 1378.24  5052.0 1380.99
  5072.3 1385.81  5098.7 1389.70  5143.6 1394.39  5203.8 1398.71  5214.8 1398.77
  5255.5 1402.45  5306.4 1412.35  5347.1 1417.30  5371.7 1419.10  5397.9 1423.49
#Mann=4,-1,0
  4778.6    0.12       0  4969.4    0.05       0  5008.4    0.05       0
  5014.2    0.05       0
Bank Sta=5008.4,5014.2
Exp/Cntr=0.3,0.1

Type RM Length L Ch R = 1,10500,500,500,500
BEGIN DESCRIPTION:
OWEN CREEK 21.0
END DESCRIPTION:
XS GIS Cut Line= 3
      2792705.68     10198903.11      2792772.75     10199261.38
      2793155.68     10199653.11
#Sta/Elev= 30
  4635.5 1429.76  4692.3 1417.99  4737.2 1408.53  4769.8 1404.76  4824.7 1386.56
  4829.8 1387.21  4877.3 1374.52  4915.0 1370.04  4995.4 1367.43  4995.9 1366.93
  5001.2 1367.43  5151.8 1381.04  5201.3 1391.86  5222.6 1392.79  5229.5 1395.62
  5265.0 1399.12  5286.1 1404.21  5293.3 1403.21  5300.3 1406.64  5307.4 1405.17
  5314.4 1408.83  5321.6 1406.76  5328.6 1408.83  5335.7 1407.73  5342.7 1410.77
  5349.9 1409.49  5371.0 1415.51  5392.3 1414.89  5512.4 1429.17  5547.8 1435.31
#Mann=6,-1,0
  4635.5    0.12       0  4692.3    0.05       0  4769.8    0.12       0
  4915.0    0.05       0  4995.4    0.05       0  5001.2    0.05       0
Bank Sta=4995.4,5001.2
Exp/Cntr=0.3,0.1

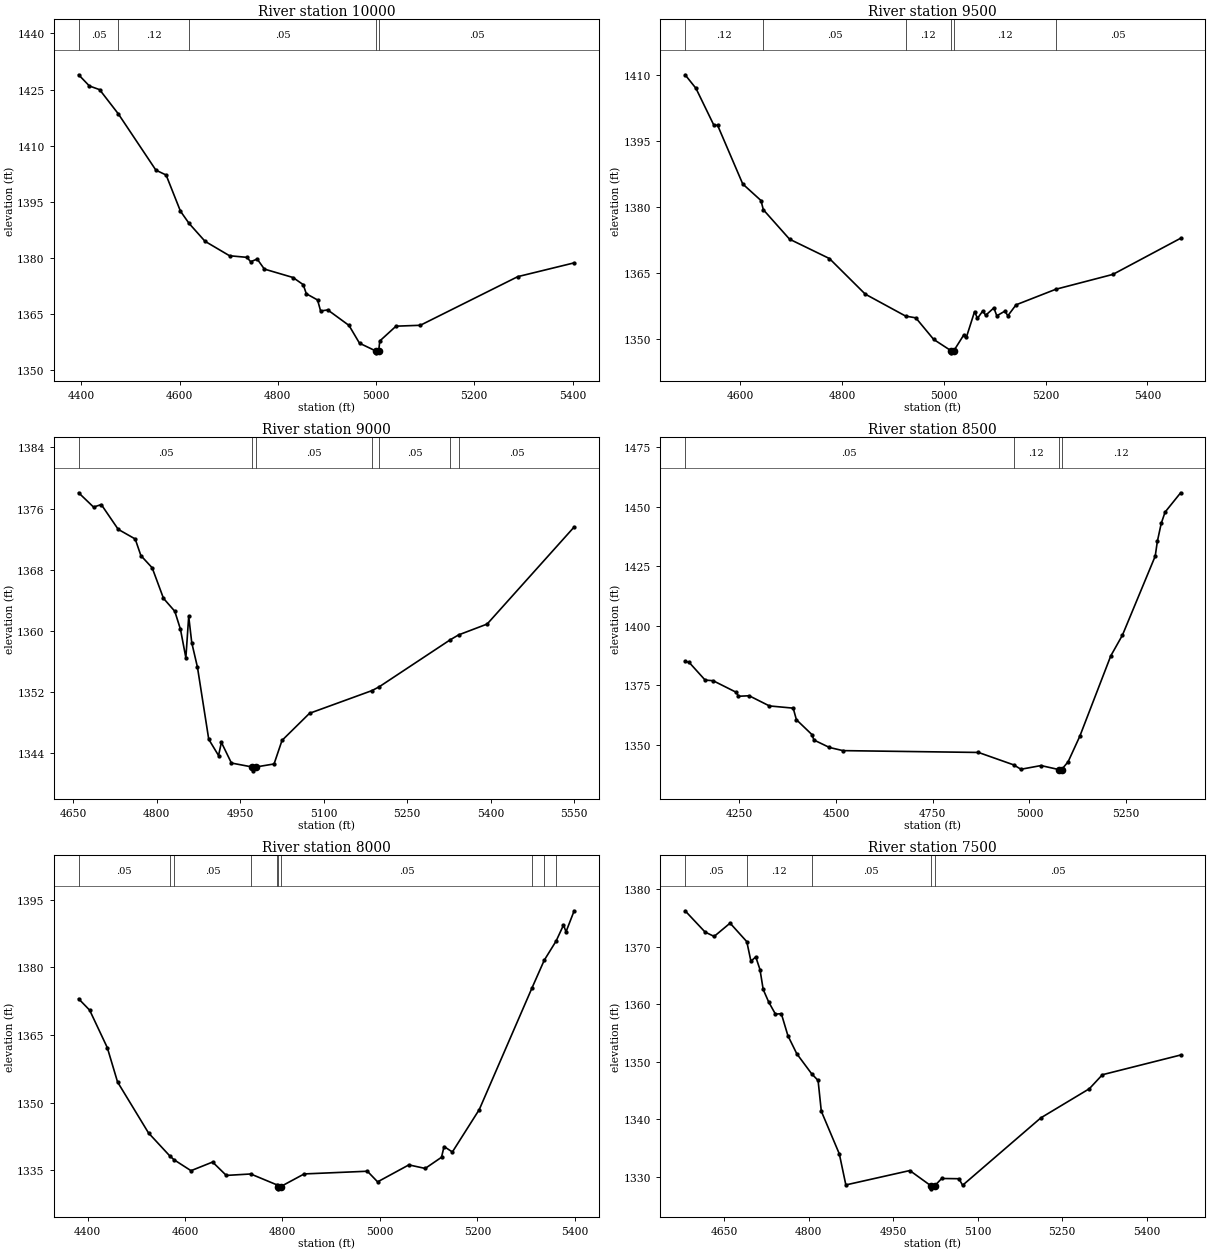
Type RM Length L Ch R = 1,10000,500,500,500
BEGIN DESCRIPTION:
OWEN CREEK 20.0
END DESCRIPTION:
XS GIS Cut Line= 3
      2791955.67     10198953.09      2792319.30     10199437.11
      2792705.66     10199553.11
#Sta/Elev= 30
  4394.6 1428.95  4416.5 1425.96  4437.3 1424.98  4475.4 1418.51  4551.9 1403.48
  4572.7 1402.18  4601.9 1392.52  4619.4 1389.26  4651.9 1384.48  4701.8 1380.62
  4737.3 1380.19  4744.8 1379.02  4758.1 1379.74  4772.7 1377.06  4831.0 1374.81
  4851.8 1372.90  4858.1 1370.47  4881.0 1368.81  4887.2 1365.87  4901.8 1366.15
  4945.0 1362.01  4966.4 1357.26  4999.5 1355.19  5000.0 1354.69  5005.4 1355.19
  5007.7 1357.86  5040.7 1361.81  5090.2 1362.05  5288.6 1375.04  5403.4 1378.72
#Mann=5,-1,0
  4394.6    0.05       0  4475.4    0.12       0  4619.4    0.05       0
  4999.5    0.05       0  5005.4    0.05       0
Bank Sta=4999.5,5005.4
Exp/Cntr=0.3,0.1

Type RM Length L Ch R = 1,9500,500,500,500
BEGIN DESCRIPTION:
OWEN CREEK 19.0
END DESCRIPTION:
XS GIS Cut Line= 3
      2791805.65     10199503.08      2792148.50     10199877.80
      2792555.72     10199653.09
#Sta/Elev= 30
  4492.1 1409.98  4513.4 1406.91  4548.6 1398.55  4556.0 1398.51  4605.3 1385.23
  4641.1 1381.48  4645.7 1379.40  4697.2 1372.72  4775.5 1368.33  4845.8 1360.27
  4925.1 1355.29  4945.1 1354.89  4980.2 1350.00  5014.0 1347.46  5014.5 1346.96
  5019.9 1347.46  5038.8 1350.93  5044.5 1350.52  5060.5 1356.31  5066.2 1354.77
  5076.6 1356.46  5082.3 1355.47  5098.4 1357.15  5104.1 1355.35  5120.1 1356.42
  5125.8 1355.35  5141.9 1357.84  5220.0 1361.37  5332.1 1364.74  5465.1 1372.93
#Mann=6,-1,0
  4492.1    0.12       0  4645.7    0.05       0  4925.1    0.12       0
  5014.0    0.07       0  5019.9    0.12       0  5220.0    0.05       0
Bank Sta=5014,5019.9
Exp/Cntr=0.3,0.1

Type RM Length L Ch R = 1,9000,500,500,500
BEGIN DESCRIPTION:
OWEN CREEK 18.0
END DESCRIPTION:
XS GIS Cut Line= 3
      2792005.68     10200203.11      2792340.48     10200263.47
      2792755.70     10199903.10
#Sta/Elev= 30
  4659.8 1378.06  4686.6 1376.19  4700.5 1376.52  4730.9 1373.28  4761.4 1372.02
  4771.6 1369.85  4791.9 1368.25  4812.2 1364.26  4832.5 1362.57  4842.7 1360.21
  4852.4 1356.49  4857.5 1361.90  4863.0 1358.45  4873.2 1355.26  4893.5 1345.83
  4911.1 1343.71  4916.2 1345.43  4934.2 1342.73  4971.8 1342.21  4972.3 1341.71
  4977.8 1342.21  5010.8 1342.61  5025.1 1345.69  5074.5 1349.23  5186.3 1352.19
  5199.3 1352.68  5327.4 1358.85  5342.2 1359.48  5393.5 1360.90  5549.8 1373.59
#Mann=7,-1,0
  4659.8    0.05       0  4971.8    0.05       0  4977.8    0.05       0
  5186.3    0.12       0  5199.3    0.05       0  5327.4    0.12       0
  5342.2    0.05       0
Bank Sta=4971.8,4977.8
Exp/Cntr=0.3,0.1

Type RM Length L Ch R = 1,8500,500,500,500
BEGIN DESCRIPTION:
OWEN CREEK 17.0
END DESCRIPTION:
XS GIS Cut Line= 3
      2791855.64     10200353.10      2792715.84     10200582.63
      2793105.73     10200553.11
#Sta/Elev= 30
  4109.7 1385.05  4120.1 1384.59  4161.5 1377.14  4182.2 1376.87  4242.3 1371.97
  4247.5 1370.33  4275.3 1370.55  4327.7 1366.27  4389.2 1365.34  4397.5 1360.48
  4437.6 1354.23  4442.8 1351.94  4482.9 1348.81  4517.8 1347.48  4868.3 1346.71
  4959.1 1341.50  4978.2 1339.64  5029.9 1341.20  5077.1 1339.48  5077.6 1338.98
  5083.1 1339.48  5100.1 1342.81  5130.2 1353.49  5210.4 1387.33  5240.5 1396.03
  5325.3 1429.27  5330.8 1435.45  5340.8 1443.02  5350.8 1447.77  5391.0 1455.89
#Mann=4,-1,0
  4109.7    0.05       0  4959.1    0.12       0  5077.1    0.07       0
  5083.1    0.12       0
Bank Sta=5077.1,5083.1
Exp/Cntr=0.3,0.1

Type RM Length L Ch R = 1,8000,500,500,500
BEGIN DESCRIPTION:
OWEN CREEK 16.0
END DESCRIPTION:
XS GIS Cut Line= 3
      2791905.71     10200503.13      2792422.93     10200841.74
      2792805.66     10200953.10
#Sta/Elev= 30
  4381.8 1373.03  4404.4 1370.51  4440.6 1362.19  4461.7 1354.55  4525.2 1343.24
  4569.1 1338.11  4577.8 1337.27  4612.4 1334.86  4656.7 1336.78  4684.8 1333.81
  4734.9 1334.13  4789.6 1331.67  4790.3 1331.33  4790.8 1330.83  4796.4 1331.33
  4844.6 1334.14  4974.3 1334.74  4995.3 1332.38  5059.4 1336.15  5092.9 1335.36
  5126.4 1337.84  5131.6 1340.22  5148.7 1339.02  5203.9 1348.44  5312.4 1375.53
  5337.2 1381.60  5361.6 1385.87  5376.7 1389.41  5381.9 1387.92  5398.6 1392.58
#Mann=10,-1,0
  4381.8    0.05       0  4569.1    0.12       0  4577.8    0.05       0
  4734.9    0.12       0  4789.6    0.05       0  4790.3    0.03       0
  4796.4    0.05       0  5312.4    0.12       0  5337.2    0.05       0
  5361.6    0.12       0
Bank Sta=4790.3,4796.4
Exp/Cntr=0.3,0.1

Type RM Length L Ch R = 1,7500,500,500,500
BEGIN DESCRIPTION:
OWEN CREEK 15.0
END DESCRIPTION:
XS GIS Cut Line= 3
      2791855.70     10200503.14      2792058.00     10200870.64
      2792455.64     10201103.09
#Sta/Elev= 30
  4580.5 1376.25  4616.0 1372.55  4632.1 1371.79  4660.4 1374.10  4690.1 1370.88
  4697.4 1367.48  4706.0 1368.23  4713.5 1366.03  4719.2 1362.57  4728.9 1360.40
  4741.0 1358.27  4751.4 1358.36  4763.1 1354.53  4778.8 1351.40  4805.0 1347.94
  4816.7 1346.74  4822.4 1341.40  4854.4 1333.98  4866.0 1328.58  4979.6 1331.08
  5017.5 1328.40  5018.0 1327.90  5023.6 1328.40  5036.2 1329.70  5066.8 1329.66
  5073.4 1328.52  5212.3 1340.24  5298.5 1345.31  5321.6 1347.74  5460.6 1351.17
#Mann=5,-1,0
  4580.5    0.05       0  4690.1    0.12       0  4805.0    0.05       0
  5017.5    0.05       0  5023.6    0.05       0
Bank Sta=5017.5,5023.6
Exp/Cntr=0.3,0.1