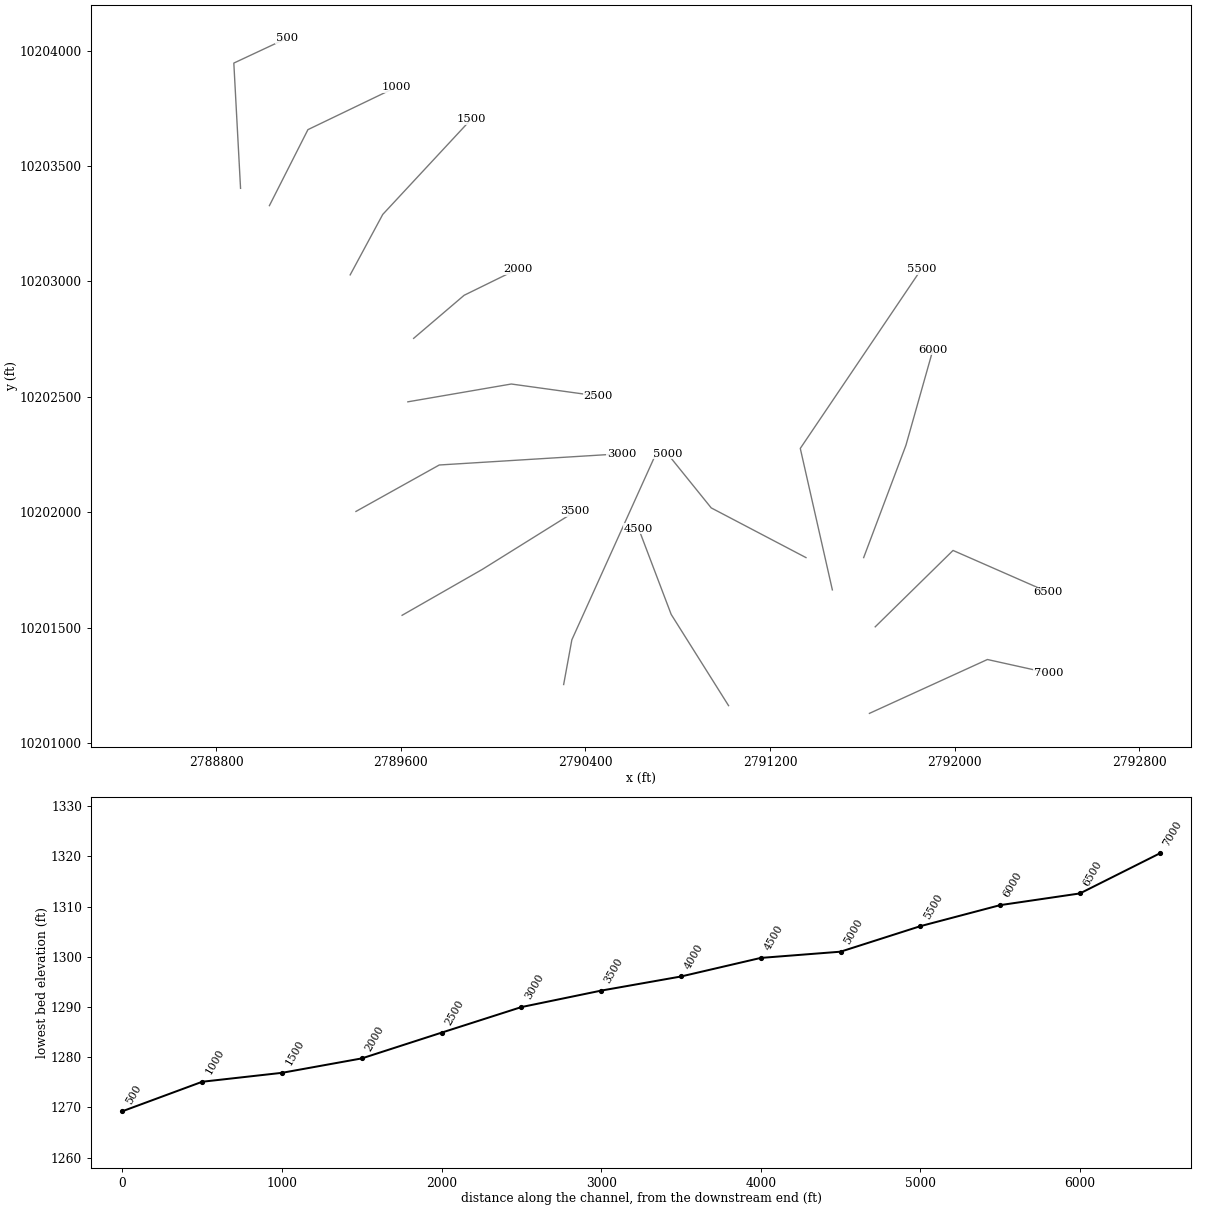
HEC-RAS study OWEN CREEK.prj: OWEN CREEK Base Level Engineering

--- OWEN CREEK.g01 (geometry) --- (continued)

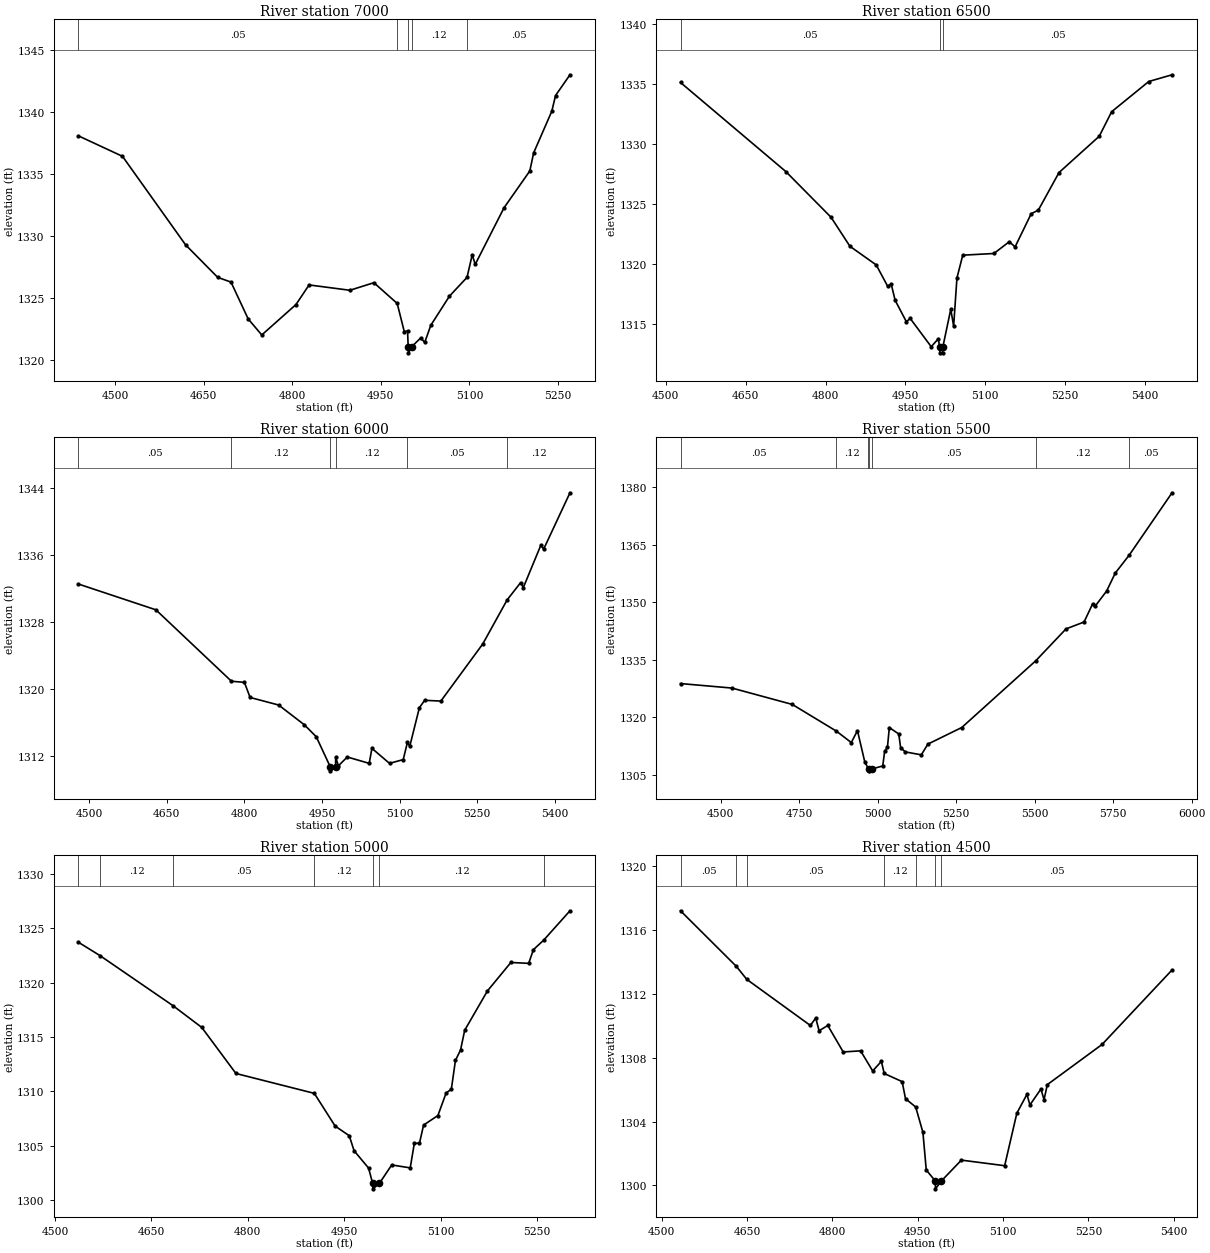
Type RM Length L Ch R = 1,7000,500,500,500
BEGIN DESCRIPTION:
OWEN CREEK 14.0
END DESCRIPTION:
XS GIS Cut Line= 3
      2791630.68     10201128.11      2792141.91     10201361.53
      2792405.72     10201303.10
#Sta/Elev= 30
  4438.0 1338.07  4512.6 1336.42  4619.4 1329.29  4673.8 1326.67  4696.3 1326.29
  4725.4 1323.32  4748.4 1322.03  4806.3 1324.48  4828.5 1326.06  4897.6 1325.63
  4938.2 1326.24  4977.7 1324.57  4989.7 1322.29  4995.2 1322.36  4996.3 1321.09
  4996.8 1320.59  5002.4 1321.09  5017.5 1321.79  5024.3 1321.43  5034.6 1322.81
  5066.2 1325.16  5095.9 1326.67  5104.7 1328.49  5109.8 1327.72  5158.6 1332.28
  5202.2 1335.24  5208.7 1336.70  5239.4 1340.05  5245.8 1341.32  5270.2 1342.99
#Mann=5,-1,0
  4438.0    0.05       0  4977.7    0.12       0  4996.3    0.07       0
  5002.4    0.12       0  5095.9    0.05       0
Bank Sta=4996.3,5002.4
Exp/Cntr=0.3,0.1

Type RM Length L Ch R = 1,6500,500,500,500
BEGIN DESCRIPTION:
OWEN CREEK 13.0
END DESCRIPTION:
XS GIS Cut Line= 3
      2791655.71     10201503.14      2791992.93     10201834.10
      2792405.69     10201653.11
#Sta/Elev= 30
  4527.5 1335.10  4725.4 1327.69  4810.3 1323.89  4845.7 1321.48  4895.1 1319.93
  4916.4 1318.17  4923.4 1318.31  4930.6 1316.99  4951.7 1315.21  4958.9 1315.48
  4998.4 1313.13  5011.7 1313.79  5014.1 1313.12  5014.6 1312.62  5019.8 1312.62
  5020.3 1313.12  5035.1 1316.24  5040.5 1314.84  5046.7 1318.84  5057.6 1320.74
  5116.1 1320.88  5145.0 1321.86  5155.9 1321.43  5186.2 1324.19  5199.5 1324.48
  5238.4 1327.61  5314.0 1330.63  5337.3 1332.67  5407.0 1335.18  5450.7 1335.74
#Mann=3,-1,0
  4527.5    0.05       0  5014.1    0.05       0  5020.3    0.05       0
Bank Sta=5014.1,5020.3
Exp/Cntr=0.3,0.1

Type RM Length L Ch R = 1,6000,500,500,500
BEGIN DESCRIPTION:
OWEN CREEK 12.0
END DESCRIPTION:
XS GIS Cut Line= 3
      2791605.68     10201803.09      2791788.91     10202290.06
      2791905.67     10202703.08
#Sta/Elev= 30
  4479.7 1332.54  4629.3 1329.47  4775.3 1320.96  4800.3 1320.83  4811.3 1319.03
  4866.4 1318.13  4916.2 1315.77  4939.1 1314.35  4966.0 1310.79  4966.5 1310.29
  4976.4 1310.79  4976.6 1311.90  4981.9 1310.89  4999.0 1311.94  5041.4 1311.18
  5046.6 1312.97  5080.6 1311.18  5107.1 1311.63  5115.2 1313.68  5119.7 1313.21
  5138.3 1317.81  5148.5 1318.69  5179.8 1318.60  5260.8 1325.41  5307.8 1330.65
  5333.9 1332.71  5339.1 1332.12  5373.1 1337.19  5378.3 1336.69  5429.2 1343.41
#Mann=6,-1,0
  4479.7    0.05       0  4775.3    0.12       0  4966.0    0.07       0
  4976.4    0.12       0  5115.2    0.05       0  5307.8    0.12       0
Bank Sta=4966,4976.4
Exp/Cntr=0.3,0.1

Type RM Length L Ch R = 1,5500,500,500,500
BEGIN DESCRIPTION:
OWEN CREEK 11.0
END DESCRIPTION:
XS GIS Cut Line= 3
      2791470.00     10201663.22      2791331.04     10202276.17
      2791855.69     10203053.12
#Sta/Elev= 30
  4371.5 1328.84  4535.4 1327.67  4727.7 1323.40  4868.4 1316.43  4915.6 1313.47
  4935.3 1316.57  4958.7 1308.38  4968.2 1306.95  4971.2 1306.60  4971.7 1306.10
  4981.6 1306.60  5015.8 1307.37  5021.9 1311.18  5030.8 1312.25  5036.8 1317.38
  5066.8 1315.71  5072.8 1312.14  5087.8 1311.03  5138.7 1310.27  5159.7 1313.07
  5267.6 1317.39  5503.1 1334.76  5599.6 1343.08  5657.2 1344.88  5684.3 1349.57
  5693.2 1349.08  5729.2 1352.96  5756.5 1357.62  5801.3 1362.33  5937.5 1378.55
#Mann=7,-1,0
  4371.5    0.05       0  4868.4    0.12       0  4968.2    0.05       0
  4971.2    0.05       0  4981.6    0.05       0  5503.1    0.12       0
  5801.3    0.05       0
Bank Sta=4971.2,4981.6
Exp/Cntr=0.3,0.1

Type RM Length L Ch R = 1,5000,500,500,500
BEGIN DESCRIPTION:
OWEN CREEK 10.0
END DESCRIPTION:
XS GIS Cut Line= 3
      2791355.70     10201803.11      2790945.06     10202018.51
      2790755.68     10202253.11
#Sta/Elev= 30
  4536.3 1323.72  4569.7 1322.50  4683.8 1317.87  4728.3 1315.88  4781.5 1311.64
  4903.5 1309.81  4935.9 1306.80  4957.9 1305.91  4965.4 1304.53  4988.0 1302.93
  4994.3 1301.52  4994.8 1301.02  5004.8 1301.52  5024.0 1303.22  5052.8 1302.95
  5059.2 1305.21  5067.2 1305.22  5073.6 1306.89  5095.9 1307.77  5108.8 1309.86
  5116.8 1310.18  5123.2 1312.84  5131.2 1313.81  5137.6 1315.62  5173.0 1319.24
  5209.5 1321.86  5237.2 1321.78  5244.7 1323.05  5260.5 1323.91  5301.5 1326.62
#Mann=7,-1,0
  4536.3    0.05       0  4569.7    0.12       0  4683.8    0.05       0
  4903.5    0.12       0  4994.3    0.05       0  5004.8    0.12       0
  5260.5    0.12       0
Bank Sta=4994.3,5004.8
Exp/Cntr=0.3,0.1

Type RM Length L Ch R = 1,4500,500,500,500
BEGIN DESCRIPTION:
OWEN CREEK 9.0
END DESCRIPTION:
XS GIS Cut Line= 3
      2791020.24     10201161.66      2790771.65     10201556.88
      2790630.68     10201928.12
#Sta/Elev= 30
  4533.1 1317.21  4631.4 1313.72  4649.6 1312.91  4761.4 1310.02  4770.8 1310.49
  4776.7 1309.69  4792.0 1310.02  4819.1 1308.36  4849.7 1308.43  4870.9 1307.17
  4886.2 1307.77  4891.2 1307.01  4922.7 1306.50  4928.6 1305.43  4946.5 1304.91
  4959.2 1303.32  4965.1 1300.96  4980.8 1300.28  4981.3 1299.78  4991.8 1300.28
  5026.8 1301.58  5102.9 1301.23  5124.3 1304.52  5142.0 1305.70  5147.3 1305.04
  5166.7 1306.04  5172.1 1305.36  5177.8 1306.31  5274.1 1308.83  5397.1 1313.50
#Mann=7,-1,0
  4533.1    0.05       0  4631.4    0.12       0  4649.6    0.05       0
  4891.2    0.12       0  4946.5    0.05       0  4980.8    0.05       0
  4991.8    0.05       0
Bank Sta=4980.8,4991.8
Exp/Cntr=0.3,0.1

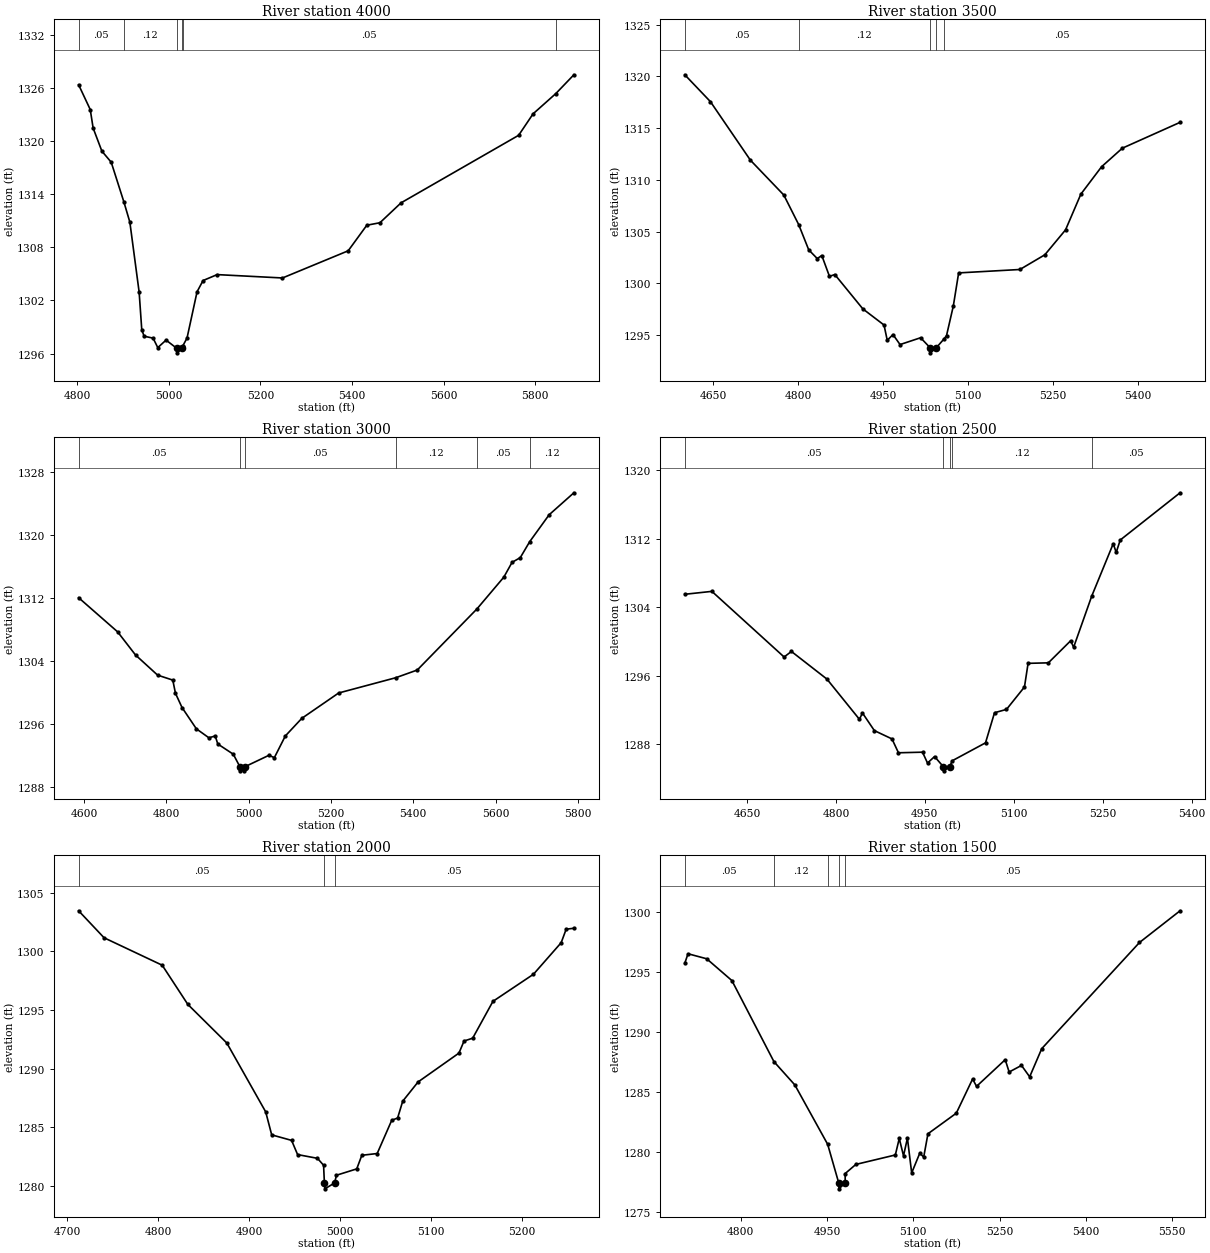
Type RM Length L Ch R = 1,4000,500,500,500
BEGIN DESCRIPTION:
OWEN CREEK 8.0
END DESCRIPTION:
XS GIS Cut Line= 3
      2790305.68     10201253.10      2790341.27     10201446.96
      2790705.69     10202253.12
#Sta/Elev= 30
  4802.9 1326.37  4828.3 1323.57  4834.6 1321.48  4853.7 1318.87  4874.1 1317.62
  4901.8 1313.13  4914.8 1310.85  4935.1 1302.94  4940.8 1298.71  4945.9 1297.96
  4965.6 1297.74  4975.8 1296.67  4993.9 1297.52  5017.5 1296.58  5018.0 1296.08
  5028.6 1296.58  5030.0 1296.82  5039.7 1297.75  5061.6 1302.98  5074.7 1304.25
  5105.5 1304.92  5248.2 1304.54  5391.7 1307.61  5432.4 1310.50  5461.0 1310.78
  5507.2 1313.03  5764.0 1320.66  5795.6 1323.09  5845.3 1325.38  5884.7 1327.50
#Mann=6,-1,0
  4802.9    0.05       0  4901.8    0.12       0  5017.5    0.07       0
  5028.6    0.12       0  5030.0    0.05       0  5845.3    0.12       0
Bank Sta=5017.5,5028.6
Exp/Cntr=0.3,0.1

Type RM Length L Ch R = 1,3500,500,500,500
BEGIN DESCRIPTION:
OWEN CREEK 7.0
END DESCRIPTION:
XS GIS Cut Line= 3
      2789605.68     10201553.11      2789952.85     10201751.78
      2790355.68     10202003.11
#Sta/Elev= 30
  4600.0 1320.16  4645.3 1317.56  4715.9 1311.90  4774.9 1308.53  4801.1 1305.68
  4818.9 1303.23  4833.9 1302.39  4842.0 1302.68  4855.5 1300.67  4865.0 1300.84
  4914.5 1297.52  4951.9 1295.96  4957.6 1294.48  4967.7 1295.04  4980.2 1294.07
  5016.5 1294.73  5033.2 1293.77  5033.7 1293.27  5044.3 1293.77  5058.3 1294.64
  5062.3 1294.94  5074.3 1297.80  5083.7 1301.00  5191.9 1301.33  5235.9 1302.75
  5272.5 1305.16  5299.6 1308.62  5336.2 1311.27  5372.8 1313.06  5474.8 1315.56
#Mann=5,-1,0
  4600.0    0.05       0  4801.1    0.12       0  5033.2    0.07       0
  5044.3    0.12       0  5058.3    0.05       0
Bank Sta=5033.2,5044.3
Exp/Cntr=0.3,0.1

Type RM Length L Ch R = 1,3000,500,500,500
BEGIN DESCRIPTION:
OWEN CREEK 6.0
END DESCRIPTION:
XS GIS Cut Line= 3
      2789405.71     10202003.13      2789766.71     10202204.36
      2790555.70     10202253.11
#Sta/Elev= 30
  4586.7 1311.99  4681.5 1307.65  4725.0 1304.71  4778.7 1302.15  4815.6 1301.52
  4822.1 1299.84  4838.1 1298.03  4872.9 1295.33  4903.3 1294.19  4918.7 1294.42
  4925.0 1293.40  4962.7 1292.10  4978.9 1290.49  4979.4 1289.99  4989.5 1289.99
  4990.0 1290.49  5049.1 1291.96  5062.5 1291.67  5089.1 1294.42  5129.2 1296.66
  5218.7 1299.88  5357.5 1301.82  5409.8 1302.80  5554.8 1310.56  5620.2 1314.60
  5640.2 1316.48  5660.2 1317.08  5683.0 1319.10  5730.4 1322.53  5790.5 1325.32
#Mann=6,-1,0
  4586.7    0.05       0  4978.9    0.05       0  4990.0    0.05       0
  5357.5    0.12       0  5554.8    0.05       0  5683.0    0.12       0
Bank Sta=4978.9,4990
Exp/Cntr=0.3,0.1

Type RM Length L Ch R = 1,2500,500,500,500
BEGIN DESCRIPTION:
OWEN CREEK 5.0
END DESCRIPTION:
XS GIS Cut Line= 3
      2789630.64     10202478.10      2790078.85     10202555.26
      2790455.65     10202503.12
#Sta/Elev= 30
  4545.2 1305.53  4590.9 1305.87  4712.7 1298.20  4725.0 1298.85  4784.9 1295.62
  4839.7 1290.92  4844.8 1291.66  4864.9 1289.60  4894.6 1288.63  4905.5 1287.01
  4946.1 1287.08  4954.5 1285.81  4966.4 1286.57  4981.0 1285.40  4981.5 1284.90
  4992.2 1285.40  4996.0 1286.07  5052.3 1288.17  5067.5 1291.69  5087.7 1292.08
  5118.0 1294.70  5124.1 1297.46  5158.3 1297.52  5195.9 1300.10  5200.9 1299.34
  5231.5 1305.33  5267.7 1311.44  5272.7 1310.42  5279.5 1311.87  5380.4 1317.39
#Mann=5,-1,0
  4545.2    0.05       0  4981.0    0.07       0  4992.2    0.05       0
  4996.0    0.12       0  5231.5    0.05       0
Bank Sta=4981,4992.2
Exp/Cntr=0.3,0.1

Type RM Length L Ch R = 1,2000,500,500,500
BEGIN DESCRIPTION:
OWEN CREEK 4.0
END DESCRIPTION:
XS GIS Cut Line= 3
      2789655.67     10202753.10      2789874.47     10202939.75
      2790105.67     10203053.11
#Sta/Elev= 30
  4712.4 1303.47  4740.4 1301.17  4804.4 1298.83  4832.6 1295.49  4875.5 1292.20
  4918.3 1286.33  4924.9 1284.37  4946.8 1283.90  4953.4 1282.69  4975.3 1282.37
  4982.0 1281.78  4982.9 1280.27  4983.4 1279.77  4994.1 1280.27  4996.2 1280.93
  5018.5 1281.47  5024.1 1282.63  5041.0 1282.78  5057.0 1285.61  5063.5 1285.81
  5069.1 1287.24  5086.0 1288.88  5131.0 1291.34  5136.6 1292.37  5146.1 1292.61
  5168.4 1295.75  5213.0 1298.06  5243.5 1300.75  5249.0 1301.90  5257.5 1301.98
#Mann=3,-1,0
  4712.4    0.05       0  4982.9    0.05       0  4994.1    0.05       0
Bank Sta=4982.9,4994.1
Exp/Cntr=0.3,0.1

Type RM Length L Ch R = 1,1500,500,500,500
BEGIN DESCRIPTION:
OWEN CREEK 3.0
END DESCRIPTION:
XS GIS Cut Line= 3
      2789380.70     10203028.14      2789521.80     10203290.05
      2789905.68     10203703.11
#Sta/Elev= 30
  4702.5 1295.75  4708.1 1296.54  4740.6 1296.12  4784.4 1294.30  4857.5 1287.53
  4893.9 1285.58  4951.0 1280.62  4970.2 1277.40  4970.7 1276.90  4981.4 1277.40
  4981.5 1278.18  5000.0 1278.94  5068.7 1279.73  5075.5 1281.11  5082.9 1279.66
  5089.7 1281.13  5097.1 1278.23  5111.2 1279.88  5118.0 1279.55  5125.4 1281.50
  5174.7 1283.22  5203.1 1286.08  5209.9 1285.46  5259.8 1287.69  5266.6 1286.66
  5288.1 1287.21  5302.3 1286.26  5323.3 1288.61  5493.3 1297.48  5563.9 1300.13
#Mann=5,-1,0
  4702.5    0.05       0  4857.5    0.12       0  4951.0    0.05       0
  4970.2    0.05       0  4981.4    0.05       0
Bank Sta=4970.2,4981.4
Exp/Cntr=0.3,0.1

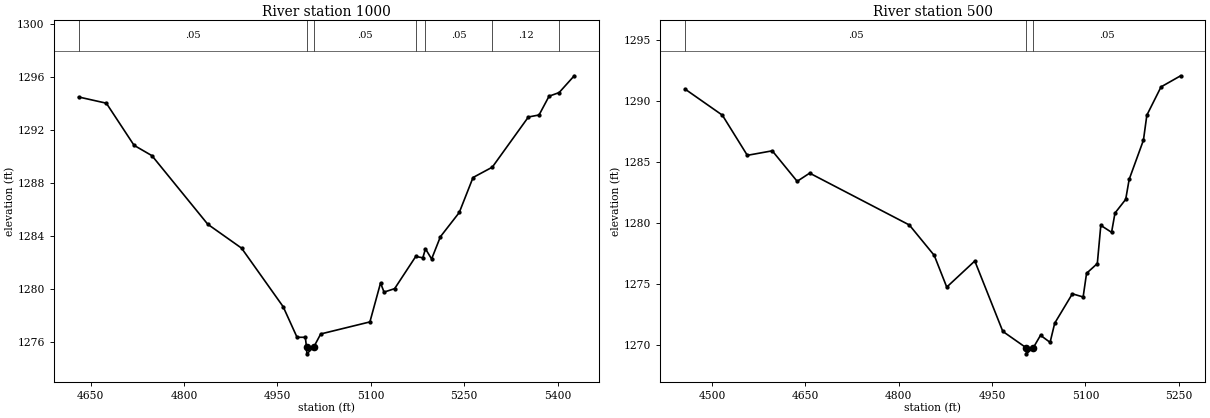
Type RM Length L Ch R = 1,1000,500,500,500
BEGIN DESCRIPTION:
OWEN CREEK 2.0
END DESCRIPTION:
XS GIS Cut Line= 3
      2789030.70     10203328.15      2789197.64     10203657.46
      2789582.09     10203842.34
#Sta/Elev= 30
  4630.8 1294.51  4675.3 1294.04  4719.8 1290.86  4748.5 1290.08  4838.2 1284.90
  4892.4 1283.10  4959.2 1278.68  4981.5 1276.37  4994.8 1276.37  4996.7 1275.62
  4997.2 1275.12  5008.2 1275.62  5019.5 1276.62  5098.5 1277.53  5115.6 1280.47
  5121.2 1279.78  5138.2 1280.04  5172.1 1282.47  5183.5 1282.37  5187.7 1283.05
  5197.6 1282.28  5211.7 1283.96  5242.0 1285.79  5264.1 1288.43  5295.0 1289.21
  5353.0 1293.00  5370.1 1293.15  5386.2 1294.57  5402.3 1294.84  5426.6 1296.11
#Mann=7,-1,0
  4630.8    0.05       0  4996.7    0.05       0  5008.2    0.05       0
  5172.1    0.12       0  5187.7    0.05       0  5295.0    0.12       0
  5402.3    0.05       0
Bank Sta=4996.7,5008.2
Exp/Cntr=0.3,0.1

Type RM Length L Ch R = 1,500,0,0,0
BEGIN DESCRIPTION:
OWEN CREEK 1.0
END DESCRIPTION:
XS GIS Cut Line= 3
      2788905.68     10203403.15      2788876.52     10203945.87
      2789105.66     10204053.10
#Sta/Elev= 30
  4456.5 1290.95  4516.5 1288.81  4556.6 1285.52  4596.7 1285.89  4636.7 1283.39
  4656.8 1284.06  4817.0 1279.81  4857.0 1277.32  4877.1 1274.72  4922.2 1276.86
  4967.2 1271.09  5004.7 1269.75  5005.2 1269.25  5016.2 1269.75  5027.8 1270.77
  5043.2 1270.19  5050.6 1271.76  5079.0 1274.17  5096.3 1273.91  5101.8 1275.85
  5119.1 1276.65  5124.7 1279.78  5142.0 1279.21  5147.5 1280.79  5164.7 1281.91
  5170.3 1283.55  5193.2 1286.76  5198.7 1288.81  5221.5 1291.13  5253.0 1292.04
#Mann=3,-1,0
  4456.5    0.05       0  5004.7    0.05       0  5016.2    0.05       0
Bank Sta=5004.7,5016.2
Exp/Cntr=0.3,0.1

Chan Stop Cuts=-1