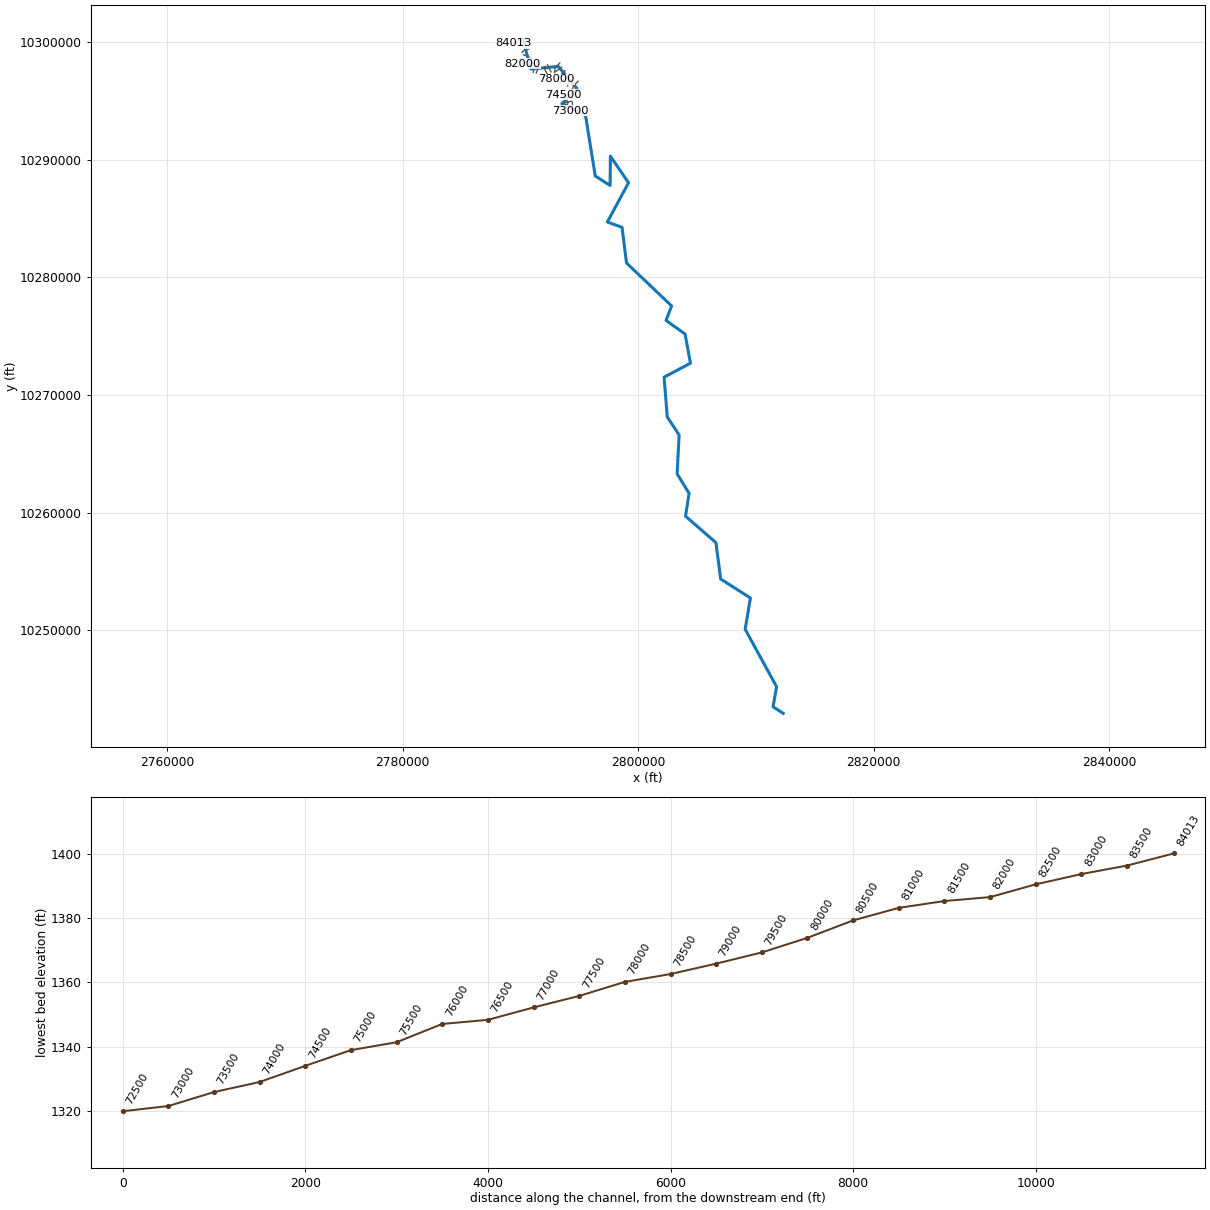
--- PECAN CREEK.prj (project) ---

Proj Title=PECAN CREEK Base Level Engineering
Current Plan=p01
Default Exp/Contr=0.3,0.1
English Units
Geom File=g01
Flow File=f01
Plan File=p01
Y Axis Title=Elevation
X Axis Title(PF)=Main Channel Distance
X Axis Title(XS)=Station
BEGIN DESCRIPTION:
PECAN CREEK
END DESCRIPTION:
DSS Export Rating Curves= 0
DSS Export Rating Curve Sorted= 0
DSS Export Volume Flow Curves= 0
DXF OffsetX= 0
DXF OffsetY= 0
DXF ScaleX= 1
DXF ScaleY= 10

--- PECAN CREEK.p01 (plan) ---

Plan Title=Multiple Run
Short Identifier=Multiple
Geom File=g01
Flow File=f01
Subcritical Flow
K Sum by GR= 0
Std Step Tol= 0.01
Critical Tol= 0.01
Num of Std Step Trials= 20
Max Error Tol= 0.3
Flow Tol Ratio= 0.001
Split Flow NTrial= 30
Split Flow Tol= 0.02
Split Flow Ratio= 0.02
Log Output Level= 0
Friction Slope Method= 1
Unsteady Friction Slope Method= 2
Unsteady Bridges Friction Slope Method= 1
Parabolic Critical Depth
Global Vel Dist=  1 , 1 , 1
Global Log Level= 0
CheckData=True
Encroach Param= -1, 0, 0, 0
BEGIN DESCRIPTION:
Multiple Run
END DESCRIPTION:

--- PECAN CREEK.f01 (steady flow) ---

Flow Title=Multiple
Program Version=4.10
Number of Profiles= 7
Profile Names=10-year,25-year,50-year,1pct_min,100-year,1pct_plu,500-year
River Rch & RM=PECAN CREEK,Reach-1         ,84013
    1300    2274    3065    2411    4235    7438    5791
River Rch & RM=PECAN CREEK,Reach-1         ,83500
    2468    4492    7174    5530   10230   18926   13929
River Rch & RM=PECAN CREEK,Reach-1         ,76500
    2973    5504    8923    6972   12824   23591   17461
River Rch & RM=PECAN CREEK,Reach-1         ,69500
    3100    5757    9410    7192   13551   25533   18459
River Rch & RM=PECAN CREEK,Reach-1         ,68000
    3637    6832   11232    8788   16250   30047   22114
River Rch & RM=PECAN CREEK,Reach-1         ,61000
    3780    7115   11696   10065   16929   28473   23013
River Rch & RM=PECAN CREEK,Reach-1         ,59500
    4011    7582   12423   10500   18010   30889   24479
River Rch & RM=PECAN CREEK,Reach-1         ,54661
    4874    9275   15181   11319   22013   42812   29713
River Rch & RM=PECAN CREEK,Reach-1         ,48500
    5202    9927   16177   14409   23474   38242   31645
River Rch & RM=PECAN CREEK,Reach-1         ,42000
    5462   10431   16975   18413   24625   32933   33137
River Rch & RM=PECAN CREEK,Reach-1         ,39930
   10312   19452   30847   26527   44074   73230   57779
River Rch & RM=PECAN CREEK,Reach-1         ,36944
   10462   19727   31188   23322   44547   85090   58355
River Rch & RM=PECAN CREEK,Reach-1         ,32000
   10779   20290   31860   27813   45430   74206   59367
River Rch & RM=PECAN CREEK,Reach-1         ,25000
   10713   20163   31603   30185   45053   67243   58851
River Rch & RM=PECAN CREEK,Reach-1         ,23646
   11211   21064   32920   26410   46865   83162   61116
River Rch & RM=PECAN CREEK,Reach-1         ,23168
   11779   22078   34296   26718   48724   88854   63374
River Rch & RM=PECAN CREEK,Reach-1         ,18000
   11897   22285   34566   26989   49081   89259   63798
River Rch & RM=PECAN CREEK,Reach-1         ,16500
   11865   22225   34454   27156   48921   88129   63585
River Rch & RM=PECAN CREEK,Reach-1         ,15000
   11884   22248   34421   27180   48855   87814   63461
River Rch & RM=PECAN CREEK,Reach-1         ,11052
   12112   22641   34906   27448   49479   89194   64176
River Rch & RM=PECAN CREEK,Reach-1         ,8546
   12306   22992   35428   27896   50201   90341   65087
River Rch & RM=PECAN CREEK,Reach-1         ,7854
   12109   22631   34861   27167   49409   89862   64071
River Rch & RM=PECAN CREEK,Reach-1         ,5926
   12364   23087   35512   27653   50300   91496   65179
River Rch & RM=PECAN CREEK,Reach-1         ,3417
   12730   23737   36431   28412   51542   93501   66705
Boundary for River Rch & Prof#=PECAN CREEK,Reach-1         , 1
Up Type= 0
Dn Type= 3
Dn Slope=0.001
Boundary for River Rch & Prof#=PECAN CREEK,Reach-1         , 2
Up Type= 0
Dn Type= 3
Dn Slope=0.001
Boundary for River Rch & Prof#=PECAN CREEK,Reach-1         , 3
Up Type= 0
Dn Type= 3
Dn Slope=0.001
Boundary for River Rch & Prof#=PECAN CREEK,Reach-1         , 4
Up Type= 0
Dn Type= 3
Dn Slope=0.001
Boundary for River Rch & Prof#=PECAN CREEK,Reach-1         , 5
Up Type= 0
Dn Type= 3
Dn Slope=0.001
Boundary for River Rch & Prof#=PECAN CREEK,Reach-1         , 6
Up Type= 0
Dn Type= 3
Dn Slope=0.001
Boundary for River Rch & Prof#=PECAN CREEK,Reach-1         , 7
Up Type= 0
Dn Type= 3
Dn Slope=0.001
DSS Import GetInterval= 0
DSS Import GetPeak= 0
DSS Import FillOption= 0

--- PECAN CREEK.g01 (geometry) ---

Geom Title=Existing Conditions
Program Version=4.10

River Reach=PECAN CREEK     ,Reach-1
Reach XY= 30
      2790221.75       10300209.      2790891.25       10297690.
      2793225.25       10297907.      2794810.25       10296043.
      2793527.25       10294742.        2795524.       10293823.
      2796361.25       10288608.       2797623.5       10287795.
        2797647.       10290283.      2799187.75       10288026.
        2797388.       10284691.      2798636.25       10284245.
      2799014.75       10281216.        2802842.       10277565.
        2802370.       10276332.       2803984.5       10275177.
      2804444.75       10272703.        2802206.       10271513.
       2802471.5       10268142.       2803478.5       10266605.
      2803311.25       10263309.       2804325.5       10261644.
        2804025.       10259703.        2806606.       10257459.
       2807007.5       10254364.      2809533.75       10252754.
      2809085.75       10250098.       2811754.5       10245214.
       2811456.5       10243510.      2812321.75       10242952.

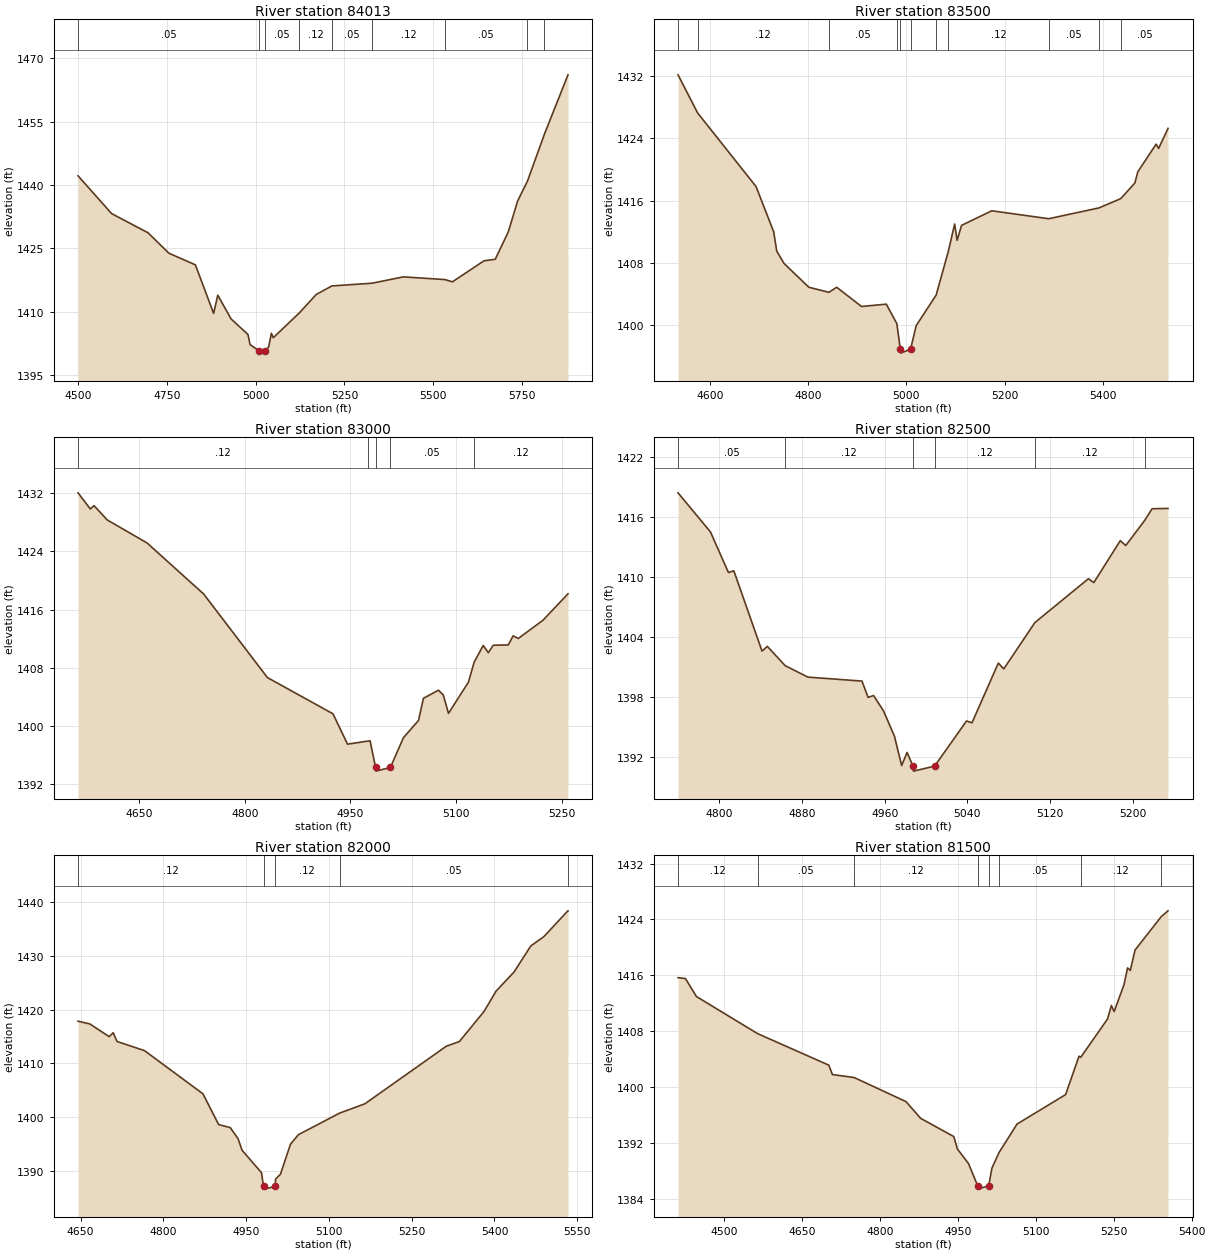
Type RM Length L Ch R = 1 ,84013   ,513,513,513
BEGIN DESCRIPTION:
PECAN CREEK 168.0
END DESCRIPTION:
XS GIS Cut Line= 3
       2790727.8      10300296.8        2790240.       10300183.
       2789405.7     10299903.12
#Sta/Elev= 30
  4499.1 1442.18  4593.7 1433.24  4696.4 1428.69  4755.1 1423.86  4829.9 1421.09
  4881.2  1409.6    4893 1413.91  4930.5 1408.29  4978.1  1404.6  4983.9 1402.22
  5009.8 1400.69  5010.3 1400.19  5025.9 1400.69  5036.2 1401.62  5044.1  1404.9
  5049.4 1403.84  5122.9 1409.72  5170.3 1414.07  5214.4  1416.1  5327.9 1416.75
  5415.9 1418.25  5533.3 1417.61  5554.1 1417.07  5643.4 1422.06    5675 1422.42
  5711.8 1428.92  5738.1 1436.23  5765.7 1440.91  5813.7 1452.07    5880  1466.1
#Mann= 9 ,-1 , 0
  4499.1     .05       0  5009.8     .05       0  5025.9     .05       0
  5122.9     .12       0  5214.4     .05       0  5327.9     .12       0
  5533.3     .05       0  5765.7     .12       0  5813.7     .05       0
Bank Sta=5009.8,5025.9
XS Rating Curve= 0 ,0
Exp/Cntr=0.3,0.1

Type RM Length L Ch R = 1 ,83500   ,500,500,500
BEGIN DESCRIPTION:
PECAN CREEK 167.0
END DESCRIPTION:
XS GIS Cut Line= 3
      2790505.67      10300003.1       2790125.5     10299736.21
      2789605.68     10299853.11
#Sta/Elev= 30
  4535.5 1432.14  4575.4 1427.24  4694.3 1417.79  4730.2 1411.98  4736.4  1409.5
  4751.2 1407.92  4801.7 1404.86  4842.7 1404.21  4858.4 1404.86  4908.9 1402.39
  4959.4 1402.69  4980.9 1400.18  4987.9  1396.9  4988.4  1396.4  5008.7  1396.9
  5020.3 1399.94  5060.9 1403.86  5085.6 1409.46  5098.5 1412.98  5103.6 1410.89
  5112.6 1412.81  5174.1 1414.68  5290.1 1413.66  5392.4 1415.05  5436.6 1416.24
  5465.3 1418.24  5471.3 1419.68  5508.6 1423.24  5513.7 1422.69  5532.8 1425.26
#Mann= 11 ,-1 , 0
  4535.5     .05       0  4575.4     .12       0  4842.7     .05       0
  4980.9     .12       0  4987.9     .07       0  5008.7     .12       0
  5060.9     .05       0  5085.6     .12       0  5290.1     .05       0
  5392.4     .12       0  5436.6     .05       0
Bank Sta=4987.9,5008.7
XS Rating Curve= 0 ,0
Exp/Cntr=0.3,0.1

Type RM Length L Ch R = 1 ,83000   ,500,500,500
BEGIN DESCRIPTION:
PECAN CREEK 166.0
END DESCRIPTION:
XS GIS Cut Line= 3
      2790755.66     10299403.11       2790333.5     10299291.38
      2790155.66     10299103.08
#Sta/Elev= 30
  4563.3 1432.07  4580.8 1429.84    4586 1430.31  4604.7 1428.34  4661.3 1425.17
  4741.7 1418.14  4832.2 1406.64  4925.3 1401.65    4946 1397.47  4974.5 1397.89
    4978 1397.93  4985.8 1394.26  4986.3 1393.76  5006.8 1394.26  5025.3 1398.36
  5046.8 1400.74  5053.7 1403.78  5075.1  1404.9    5082 1404.23  5089.3 1401.71
  5117.6    1406  5125.8 1408.77  5138.6 1411.06  5145.9 1410.06  5152.8 1411.09
  5174.2 1411.13  5181.1 1412.38  5188.4 1412.02  5223.6 1414.54    5259 1418.17
#Mann= 5 ,-1 , 0
  4563.3     .12       0  4974.5     .05       0  4985.8     .05       0
  5006.8     .05       0  5125.8     .12       0
Bank Sta=4985.8,5006.8
XS Rating Curve= 0 ,0
Exp/Cntr=0.3,0.1

Type RM Length L Ch R = 1 ,82500   ,500,500,500
BEGIN DESCRIPTION:
PECAN CREEK 165.0
END DESCRIPTION:
XS GIS Cut Line= 3
      2790705.68     10298753.11      2790476.47     10298824.59
      2790255.71      10298903.1
#Sta/Elev= 30
  4759.9 1418.37  4791.3 1414.46  4808.7  1410.4  4813.9 1410.58  4841.2 1402.55
  4846.4 1403.02  4863.5  1401.1  4885.6 1399.95    4938 1399.55  4943.9 1397.92
  4949.2 1398.11  4958.9 1396.56  4969.4 1394.05  4976.4 1391.11  4981.7 1392.42
  4987.3 1391.05  4987.8 1390.55  5008.3 1391.05  5039.2 1395.56  5044.5 1395.38
    5070 1401.35  5075.3 1400.77  5105.4  1405.4  5157.2 1409.78  5162.5  1409.4
  5188.1 1413.59  5193.4  1413.1  5211.9 1415.64  5218.9 1416.78  5234.3 1416.81
#Mann= 6 ,-1 , 0
  4759.9     .05       0  4863.5     .12       0  4987.3     .05       0
  5008.3     .12       0  5105.4     .12       0  5211.9     .05       0
Bank Sta=4987.3,5008.3
XS Rating Curve= 0 ,0
Exp/Cntr=0.3,0.1

Type RM Length L Ch R = 1 ,82000   ,500,500,500
BEGIN DESCRIPTION:
PECAN CREEK 164.0
END DESCRIPTION:
XS GIS Cut Line= 3
       2790905.7     10298603.13      2790646.86     10298360.77
      2790155.65      10298153.1
#Sta/Elev= 30
  4645.4 1417.83  4666.7 1417.33  4701.9 1414.96  4709.2 1415.69    4716 1414.06
  4765.8 1412.36  4871.8 1404.32  4900.2  1398.6  4921.2 1398.03  4935.3 1395.98
  4942.7 1393.81  4977.8 1389.65  4981.5 1387.08    4982 1386.58  5002.6 1387.08
  5003.4 1388.45  5012.2 1389.35  5030.5 1394.96  5044.7 1396.71  5119.4 1400.73
  5165.2 1402.46  5312.8 1413.18  5336.5 1414.05  5381.3 1419.67    5403 1423.44
  5435.6    1427  5465.9 1431.85  5489.6 1433.58  5533.1 1438.38  5533.3 1438.38
#Mann= 5 ,-1 , 0
  4645.4     .12       0  4981.5     .07       0  5002.6     .12       0
  5119.4     .05       0  5533.1     .12       0
Bank Sta=4981.5,5002.6
XS Rating Curve= 0 ,0
Exp/Cntr=0.3,0.1

Type RM Length L Ch R = 1 ,81500   ,500,500,500
BEGIN DESCRIPTION:
PECAN CREEK 163.0
END DESCRIPTION:
XS GIS Cut Line= 3
      2791205.71     10298303.14      2790790.59     10297886.85
       2790455.7     10298003.11
#Sta/Elev= 30
  4412.1 1415.64  4426.3 1415.52  4447.5 1412.94  4565.3 1407.62  4702.1 1403.11
  4709.1 1401.76  4750.8 1401.34  4850.5 1397.89  4878.8 1395.49  4942.5 1392.88
  4949.5 1391.09  4970.8 1389.01  4988.3 1385.85  4988.8 1385.35  5009.7 1385.85
  5015.8 1388.36  5029.6  1390.6  5064.1 1394.67  5157.5 1398.89  5183.3 1404.39
  5186.6 1404.23  5238.1 1409.72  5245.6 1411.66  5250.9 1410.78  5269.8 1414.63
  5276.7 1417.04    5282 1416.68    5291 1419.59  5341.6  1424.4  5354.5 1425.22
#Mann= 8 ,-1 , 0
  4412.1     .12       0  4565.3     .05       0  4750.8     .12       0
  4988.3     .07       0  5009.7     .12       0  5029.6     .05       0
  5186.6     .12       0  5341.6     .05       0
Bank Sta=4988.3,5009.7
XS Rating Curve= 0 ,0
Exp/Cntr=0.3,0.1

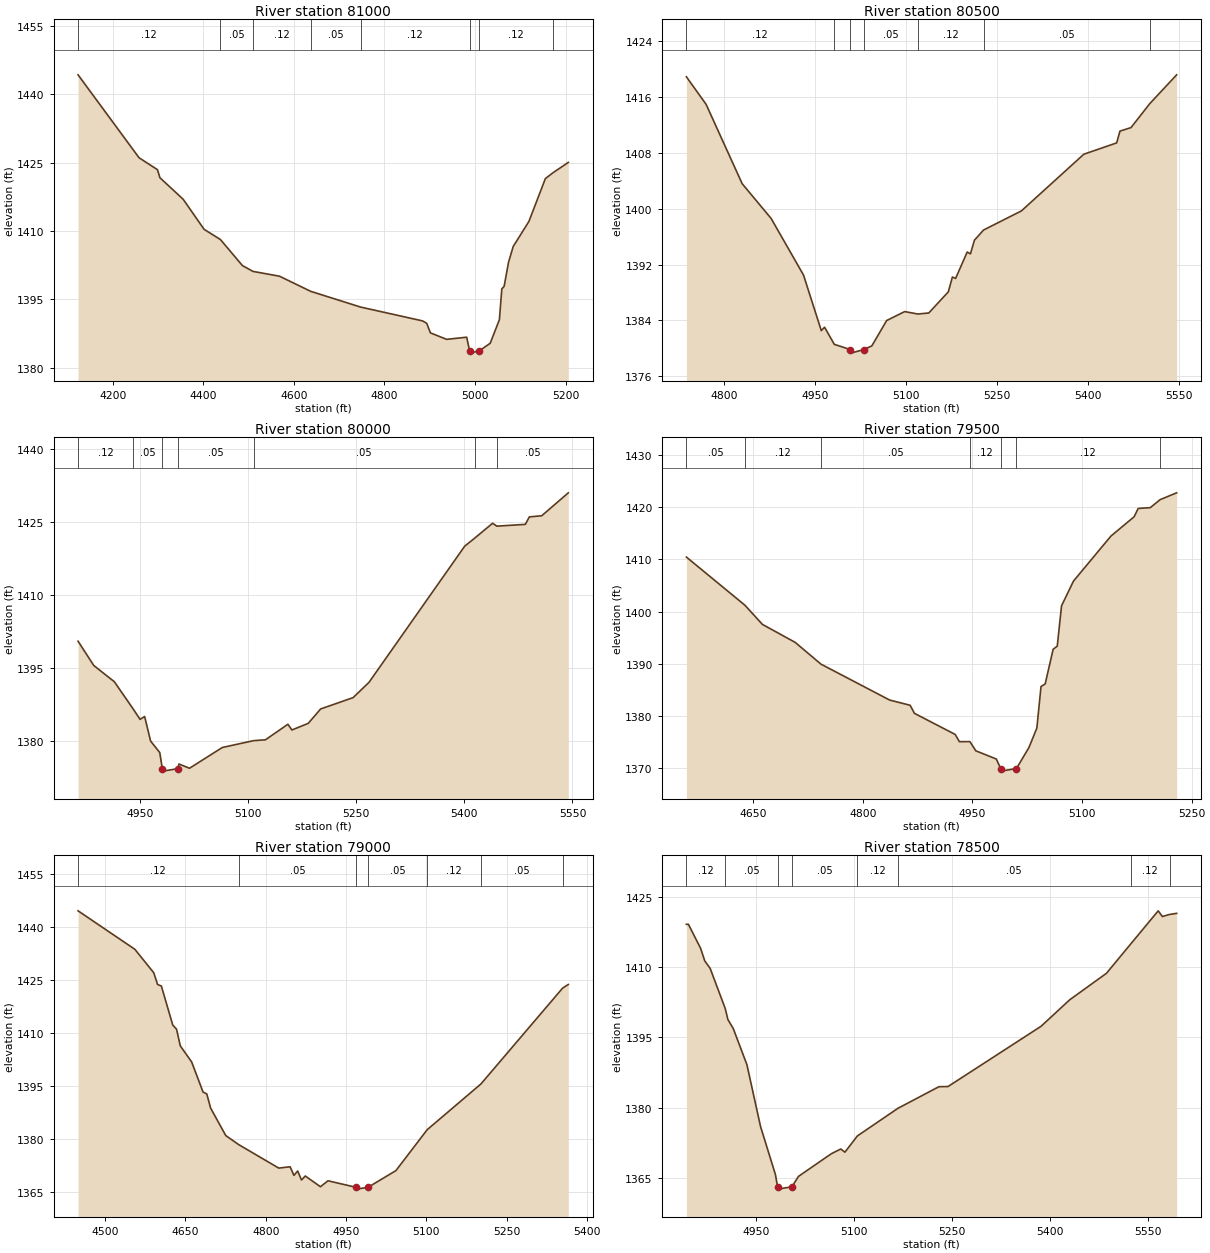
Type RM Length L Ch R = 1 ,81000   ,500,500,500
BEGIN DESCRIPTION:
PECAN CREEK 162.0
END DESCRIPTION:
XS GIS Cut Line= 3
      2791505.68     10298403.09      2791140.85     10297606.24
      2791105.69     10297403.16
#Sta/Elev= 30
  4123.6 1444.24  4258.4 1426.05  4298.9 1423.45  4304.4 1421.68  4355.9 1416.94
  4401.9 1410.37  4437.9 1408.14  4486.5 1402.43  4509.7 1401.15  4568.5 1400.09
  4637.2 1396.78  4747.4 1393.33  4884.1  1390.3  4893.5 1389.77  4901.6 1387.67
  4937.4 1386.25  4981.7 1386.72  4988.2 1383.73  4988.7 1383.23  5009.7 1383.73
  5033.6 1385.39  5053.9 1390.55  5059.3 1397.31  5064.4 1397.88  5074.2 1403.18
  5084.4  1406.6  5119.1  1412.1  5155.4 1421.48  5171.5 1422.72  5206.1 1425.04
#Mann= 8 ,-1 , 0
  4123.6     .12       0  4437.9     .05       0  4509.7     .12       0
  4637.2     .05       0  4747.4     .12       0  4988.2     .07       0
  5009.7     .12       0  5171.5     .05       0
Bank Sta=4988.2,5009.7
XS Rating Curve= 0 ,0
Exp/Cntr=0.3,0.1

Type RM Length L Ch R = 1 ,80500   ,500,500,500
BEGIN DESCRIPTION:
PECAN CREEK 161.0
END DESCRIPTION:
XS GIS Cut Line= 3
      2791655.69     10298103.14      2791555.94     10297861.41
      2791355.69     10297353.14
#Sta/Elev= 30
  4738.5  1418.9    4771 1414.95  4830.4 1403.59  4878.2  1398.6  4931.5  1390.5
  4960.8 1382.54  4966.2 1383.03  4982.2 1380.58  5008.9 1379.82  5009.4 1379.32
  5030.4 1379.82  5044.1 1380.36  5068.5 1383.99  5098.2 1385.27  5119.8 1384.92
  5137.9 1385.07  5170.1  1388.1  5176.8 1390.22  5182.1 1390.02  5201.2  1393.8
  5206.5 1393.54  5213.1 1395.49  5228.1 1396.95  5290.5 1399.69  5393.4 1407.81
  5447.5 1409.43  5452.9 1411.12  5471.1 1411.62  5502.1 1415.06  5546.3 1419.18
#Mann= 7 ,-1 , 0
  4738.5     .12       0  4982.2     .05       0  5008.9     .05       0
  5030.4     .05       0  5119.8     .12       0  5228.1     .05       0
  5502.1     .12       0
Bank Sta=5008.9,5030.4
XS Rating Curve= 0 ,0
Exp/Cntr=0.3,0.1

Type RM Length L Ch R = 1 ,80000   ,500,500,500
BEGIN DESCRIPTION:
PECAN CREEK 160.0
END DESCRIPTION:
XS GIS Cut Line= 3
      2792105.68     10297903.11      2792022.83       10297795.
      2792255.67     10297303.13
#Sta/Elev= 30
  4863.8 1400.52  4885.6 1395.55  4914.2 1392.21  4939.7 1386.77  4949.9  1384.5
  4956.2  1385.1  4964.5 1380.06  4977.2  1377.7  4980.8  1374.4  4981.3  1373.9
  5002.4  1374.4  5003.8 1375.36  5018.5 1374.49    5064 1378.74  5107.6 1380.15
  5123.8 1380.31    5155  1383.5  5160.6 1382.33  5183.3 1383.69  5200.5 1386.64
  5245.5 1388.96  5267.6 1392.09  5400.4 1419.99  5414.4 1421.65  5439.1 1424.68
  5445.1 1424.09  5484.6 1424.46  5490.1 1425.99  5507.3 1426.22  5544.2 1430.92
#Mann= 7 ,-1 , 0
  4863.8     .12       0  4939.7     .05       0  4980.8     .07       0
  5002.4     .05       0  5107.6     .05       0  5414.4     .12       0
  5445.1     .05       0
Bank Sta=4980.8,5002.4
XS Rating Curve= 0 ,0
Exp/Cntr=0.3,0.1

Type RM Length L Ch R = 1 ,79500   ,500,500,500
BEGIN DESCRIPTION:
PECAN CREEK 159.0
END DESCRIPTION:
XS GIS Cut Line= 3
      2792305.66     10298053.15      2792500.56       10297657.
      2792605.69     10297453.11
#Sta/Elev= 30
  4558.5 1410.46  4638.6 1401.21  4662.5 1397.53  4707.4 1394.07  4742.7 1389.89
  4836.7 1382.99  4864.7 1381.99  4870.6 1380.44  4926.3 1376.39  4932.1    1375
  4946.5 1375.01  4954.6 1373.24  4982.6 1371.67  4988.6 1369.84  4989.1 1369.34
  5010.2 1369.84  5027.3 1373.88  5038.1 1377.61  5043.8 1385.59  5049.5 1386.09
  5060.4 1392.75    5066 1393.34  5071.9  1401.1  5088.2 1405.84  5139.4 1414.48
  5171.2  1418.2  5176.8  1419.8  5193.3 1419.95  5206.8 1421.49  5229.4  1422.8
#Mann= 7 ,-1 , 0
  4558.5     .05       0  4638.6     .12       0  4742.7     .05       0
  4946.5     .12       0  4988.6     .07       0  5010.2     .12       0
  5206.8     .05       0
Bank Sta=4988.6,5010.2
XS Rating Curve= 0 ,0
Exp/Cntr=0.3,0.1

Type RM Length L Ch R = 1 ,79000   ,500,500,500
BEGIN DESCRIPTION:
PECAN CREEK 158.0
END DESCRIPTION:
XS GIS Cut Line= 3
       2793355.7     10298203.13      2792967.59     10297812.86
      2792905.69     10297453.15
#Sta/Elev= 30
  4449.6 1444.48  4555.7 1433.61    4591 1426.97  4598.1 1423.67  4605.2 1423.23
  4626.4 1412.22  4633.5 1411.04  4640.5 1406.33  4661.7 1401.79    4683 1393.28
    4690 1392.74  4697.1 1388.76  4725.4 1380.99  4749.5 1378.43  4824.4 1371.79
  4845.6 1372.17  4852.7 1369.73  4859.7 1370.98  4866.8 1368.43  4873.9 1369.56
  4902.2 1366.53  4916.3 1368.21    4969 1366.35  4969.5 1365.85  4990.9 1366.35
  5043.1 1371.08  5101.5 1382.64  5201.9 1395.57  5354.4 1422.65    5365 1423.67
#Mann= 7 ,-1 , 0
  4449.6     .12       0  4749.5     .05       0    4969     .03       0
  4990.9     .05       0  5101.5     .12       0  5201.9     .05       0
  5354.4     .12       0
Bank Sta=4969,4990.9
XS Rating Curve= 0 ,0
Exp/Cntr=0.3,0.1

Type RM Length L Ch R = 1 ,78500   ,500,500,500
BEGIN DESCRIPTION:
PECAN CREEK 157.0
END DESCRIPTION:
XS GIS Cut Line= 3
      2793505.67      10297853.1      2793380.85     10297758.52
      2792905.67      10297403.1
#Sta/Elev= 30
  4843.4 1419.11  4846.5 1419.11  4865.2 1413.97  4871.5  1411.3  4879.8 1409.69
  4902.9 1401.11  4906.9 1398.79  4915.1 1396.87    4936 1389.16  4956.8 1375.99
  4979.6 1365.72  4982.9 1363.11  4983.4 1362.61  5004.8 1363.11    5015 1365.34
  5065.1 1370.16  5079.6 1371.17  5085.9 1370.49    5105 1373.96  5166.9 1379.84
  5229.7 1384.46  5243.7  1384.5    5386 1397.35  5429.8    1403    5486 1408.65
  5523.2 1414.92  5565.2 1421.98  5571.5 1420.77  5582.7 1421.21  5593.4 1421.44
#Mann= 8 ,-1 , 0
  4843.4     .12       0  4902.9     .05       0  4982.9     .05       0
  5004.8     .05       0    5105     .12       0  5166.9     .05       0
  5523.2     .12       0  5582.7     .05       0
Bank Sta=4982.9,5004.8
XS Rating Curve= 0 ,0
Exp/Cntr=0.3,0.1

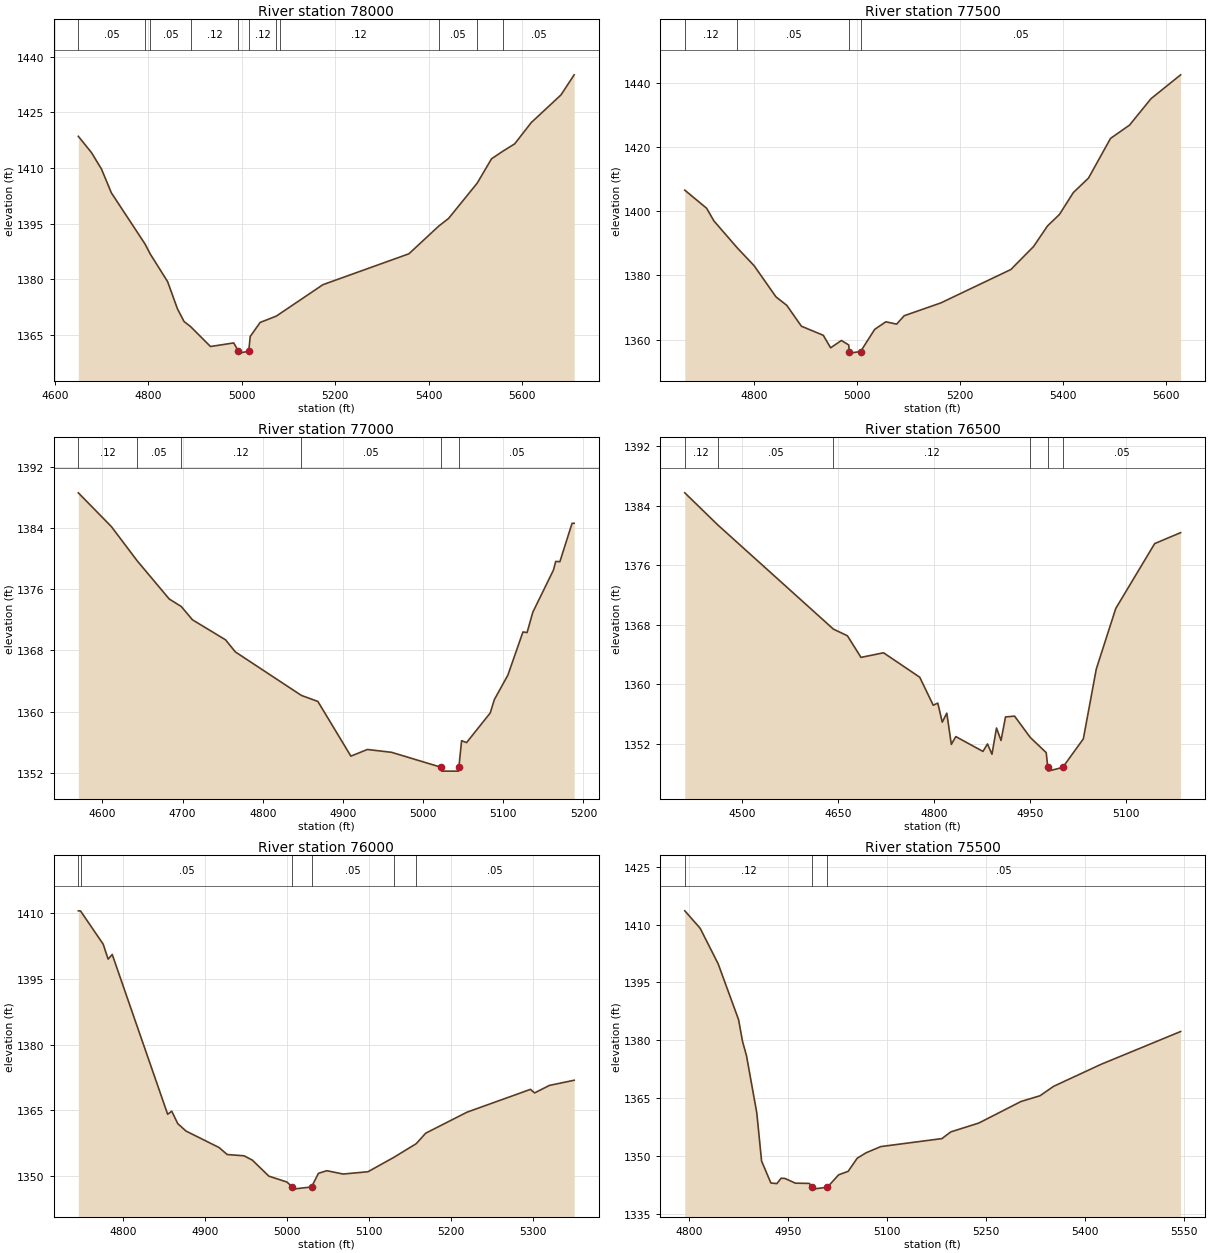
Type RM Length L Ch R = 1 ,78000   ,500,500,500
BEGIN DESCRIPTION:
PECAN CREEK 156.0
END DESCRIPTION:
XS GIS Cut Line= 3
      2793805.68      10297553.1      2793562.18     10297302.38
      2793055.69     10296803.11
#Sta/Elev= 30
  4650.5 1418.53  4678.7 1414.13    4700 1409.72  4721.1 1403.33  4793.3 1389.52
  4804.1  1386.9  4841.5 1379.41  4862.6 1372.08  4876.7 1368.67  4890.6 1367.31
  4933.3 1361.94  4982.9 1362.91  4993.1 1360.66  4993.6 1360.16    5015 1360.66
  5018.2 1364.63  5039.4 1368.42    5074 1370.12  5080.9 1370.71  5173.8 1378.59
  5357.7  1386.9  5421.4 1394.35  5442.5 1396.41  5503.9 1405.94  5534.4 1412.47
  5559.8 1414.61    5584  1416.5  5619.3 1422.21    5683 1429.67  5711.2 1435.08
#Mann= 11 ,-1 , 0
  4650.5     .05       0  4793.3     .12       0  4804.1     .05       0
  4890.6     .12       0  4993.1     .07       0    5015     .12       0
    5074     .05       0  5080.9     .12       0  5421.4     .05       0
  5503.9     .12       0  5559.8     .05       0
Bank Sta=4993.1,5015
XS Rating Curve= 0 ,0
Exp/Cntr=0.3,0.1

Type RM Length L Ch R = 1 ,77500   ,500,500,500
BEGIN DESCRIPTION:
PECAN CREEK 155.0
END DESCRIPTION:
XS GIS Cut Line= 3
       2794055.7     10297103.13       2793813.7     10296873.23
      2793305.72     10296503.14
#Sta/Elev= 30
  4666.2 1406.59  4708.5 1400.96  4722.7 1397.01  4768.4 1388.53  4800.7 1383.05
  4843.2 1373.32  4864.2 1370.67  4892.5 1364.18    4935 1361.35  4949.2 1357.45
  4970.2 1359.73  4984.4 1358.33  4985.5 1356.29    4986 1355.79  5007.4 1356.29
  5034.7 1363.19  5056.4 1365.56  5077.3 1364.83    5092 1367.45  5163.1 1371.44
    5299 1381.85  5343.1 1389.02  5370.1 1395.43  5393.3 1399.01  5420.3 1405.85
  5449.7 1410.35  5492.4 1422.71  5529.3 1426.86    5571  1435.1  5628.5 1442.54
#Mann= 4 ,-1 , 0
  4666.2     .12       0  4768.4     .05       0  4985.5     .05       0
  5007.4     .05       0
Bank Sta=4985.5,5007.4
XS Rating Curve= 0 ,0
Exp/Cntr=0.3,0.1

Type RM Length L Ch R = 1 ,77000   ,500,500,500
BEGIN DESCRIPTION:
PECAN CREEK 154.0
END DESCRIPTION:
XS GIS Cut Line= 3
      2794155.69     10296853.15      2794052.27     10296435.67
      2794005.69     10296253.12
#Sta/Elev= 30
  4569.9 1388.59  4611.1 1384.18  4643.5 1379.68  4683.3 1374.71  4698.3 1373.73
  4712.3 1371.99  4753.6 1369.37  4765.7  1367.8  4848.1 1362.11  4868.7 1361.32
  4909.9 1354.17  4930.5 1355.04  4960.6 1354.67  5022.6 1352.71  5023.1 1352.21
  5044.1 1352.21  5044.6 1352.71    5048 1356.19  5054.2 1355.94  5083.7 1359.81
  5088.8 1361.55  5105.8 1364.78  5124.5  1370.4  5129.7 1370.33  5136.8 1372.98
  5162.6  1378.5  5165.4 1379.62  5170.6 1379.59  5185.8 1384.61  5188.4 1384.61
#Mann= 6 ,-1 , 0
  4569.9     .12       0  4643.5     .05       0  4698.3     .12       0
  4848.1     .05       0  5022.6     .05       0  5044.6     .05       0
Bank Sta=5022.6,5044.6
XS Rating Curve= 0 ,0
Exp/Cntr=0.3,0.1

Type RM Length L Ch R = 1 ,76500   ,500,500,500
BEGIN DESCRIPTION:
PECAN CREEK 153.0
END DESCRIPTION:
XS GIS Cut Line= 3
      2794905.68     10296653.11        2794488.      10296236.4
      2794455.69     10296053.12
#Sta/Elev= 30
    4410 1385.73  4461.5 1381.43  4642.6 1367.42  4664.5 1366.53  4685.8 1363.62
  4721.1 1364.24  4777.7 1360.96  4798.9 1357.19    4806 1357.48    4813 1354.92
  4820.1 1356.13  4827.2 1351.93  4834.2 1352.98  4876.7 1350.99  4883.8 1351.99
  4890.8 1350.61  4897.9 1354.13    4905 1352.46    4912 1355.62  4926.2 1355.73
  4950.8 1352.86  4975.7 1350.83  4978.2 1348.84  4978.7 1348.34  5001.5 1348.84
  5033.8 1352.67  5054.1 1362.06  5084.6  1370.2  5145.5 1378.91  5186.1 1380.38
#Mann= 6 ,-1 , 0
    4410     .12       0  4461.5     .05       0  4642.6     .12       0
  4950.8     .05       0  4978.2     .05       0  5001.5     .05       0
Bank Sta=4978.2,5001.5
XS Rating Curve= 0 ,0
Exp/Cntr=0.3,0.1

Type RM Length L Ch R = 1 ,76000   ,500,500,500
BEGIN DESCRIPTION:
PECAN CREEK 152.0
END DESCRIPTION:
XS GIS Cut Line= 3
      2795105.72     10295903.11      2794853.93     10295937.27
       2794505.7     10295903.11
#Sta/Elev= 30
  4745.9 1410.52  4748.6 1410.49  4776.2 1402.91  4782.2 1399.51  4787.2 1400.57
  4854.7 1364.13  4859.7 1364.83    4867    1362  4877.1  1360.3  4917.5 1356.53
  4927.2 1354.95  4947.8 1354.66  4957.9 1353.67    4978 1350.02    5000 1348.68
  5006.6 1347.56  5007.1 1347.06    5030 1347.56  5038.4 1350.66  5048.5 1351.26
  5068.6  1350.5  5098.8 1351.03  5130.3 1354.31  5157.5 1357.42    5169 1359.81
  5219.3  1364.6  5296.7 1369.81  5301.7    1369  5319.8 1370.71  5349.9 1371.89
#Mann= 6 ,-1 , 0
  4745.9     .12       0  4748.6     .05       0  5006.6     .05       0
    5030     .05       0  5130.3     .12       0  5157.5     .05       0
Bank Sta=5006.6,5030
XS Rating Curve= 0 ,0
Exp/Cntr=0.3,0.1

Type RM Length L Ch R = 1 ,75500   ,500,500,500
BEGIN DESCRIPTION:
PECAN CREEK 151.0
END DESCRIPTION:
XS GIS Cut Line= 3
      2794805.69      10295353.1      2794699.89     10295530.91
      2794355.71     10295953.08
#Sta/Elev= 30
  4793.1 1413.59  4816.4 1409.06  4843.7 1399.83  4874.6 1385.36  4880.7 1379.64
  4886.6 1376.02  4902.2 1361.21  4909.5 1348.66  4923.6 1342.96  4932.7 1342.81
  4939.2 1344.21    4945 1344.14  4960.6 1342.92    4982 1342.85  4985.9 1341.87
  4986.4 1341.37  5009.3 1341.87  5026.3 1345.09  5040.7 1345.99  5054.5  1349.4
  5067.9  1350.8  5090.2 1352.41  5182.8 1354.48  5196.4 1356.23  5238.8 1358.52
  5302.7 1364.11  5331.5  1365.6  5352.3 1368.06  5424.1 1373.76  5544.7 1382.27
#Mann= 3 ,-1 , 0
  4793.1     .12       0  4985.9     .05       0  5009.3     .05       0
Bank Sta=4985.9,5009.3
XS Rating Curve= 0 ,0
Exp/Cntr=0.3,0.1

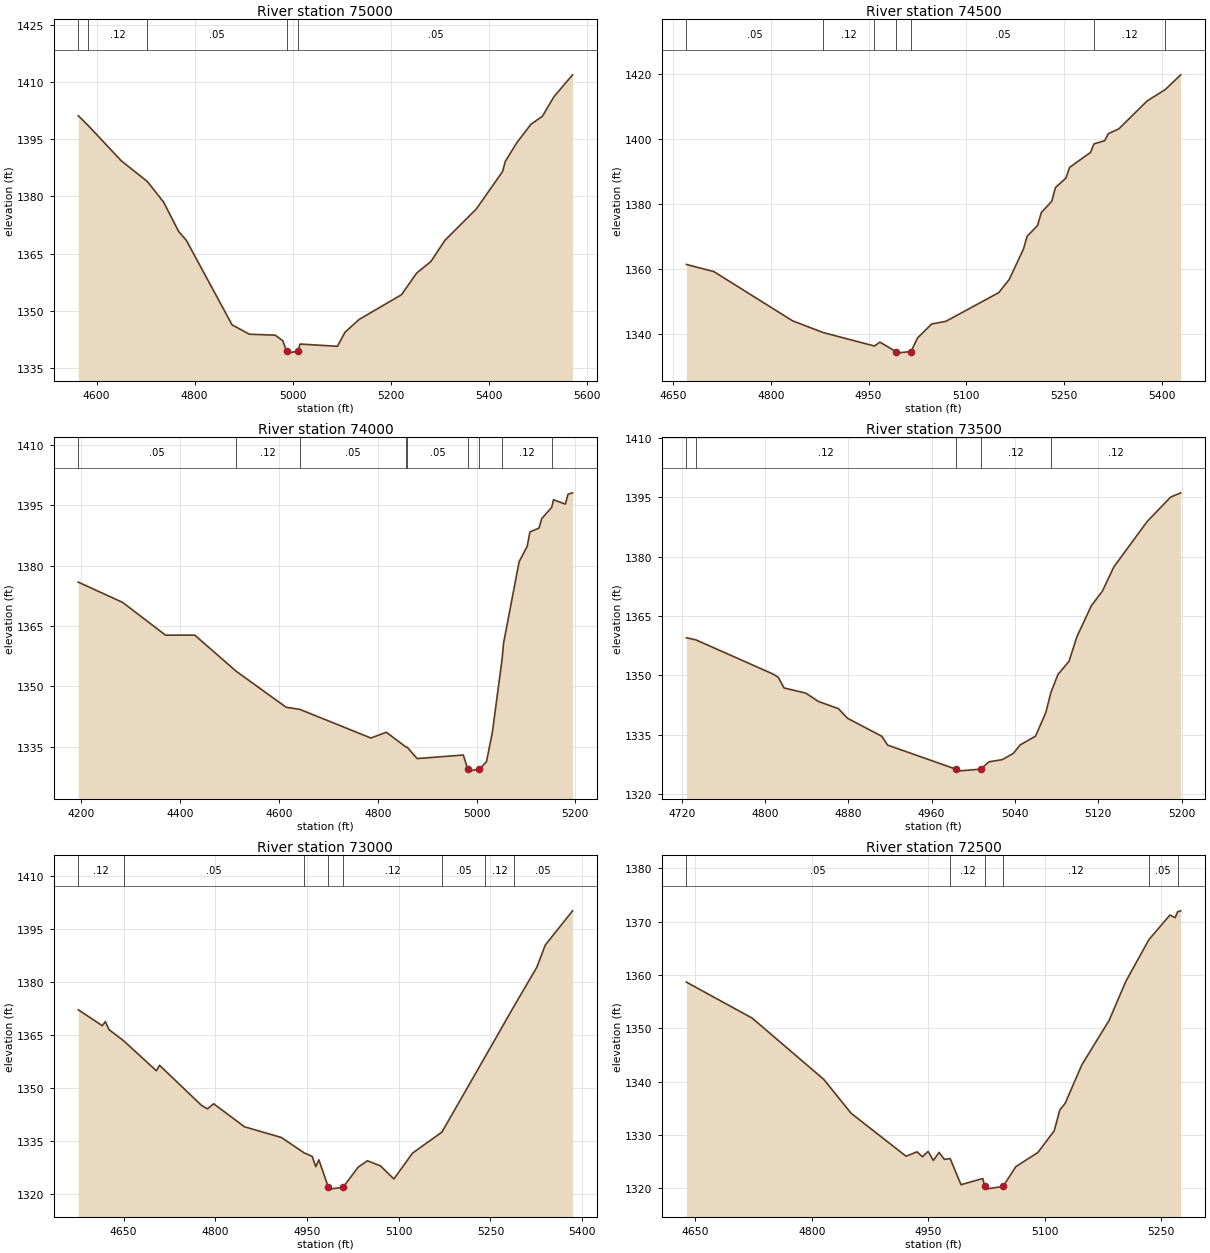
Type RM Length L Ch R = 1 ,75000   ,500,500,500
BEGIN DESCRIPTION:
PECAN CREEK 150.0
END DESCRIPTION:
XS GIS Cut Line= 3
      2794605.69     10295153.11       2794229.4      10295375.9
      2793705.67     10295603.12
#Sta/Elev= 30
  4562.7 1401.16  4583.5 1398.52  4650.5 1389.32  4703.9 1383.88    4737 1378.46
  4767.4 1370.82  4783.1 1368.49  4876.5 1346.31  4911.7 1343.87  4964.4 1343.62
    4980 1342.15  4987.6 1339.41  4988.1 1338.91    5011 1339.41    5015 1341.29
  5091.3  1340.7  5106.8 1344.39  5135.7 1347.75  5222.1 1354.24  5253.1 1359.93
    5282 1362.94  5310.9 1368.53  5374.7 1376.72  5428.2 1386.53  5433.7 1389.18
  5457.1 1394.06    5486 1398.91  5509.5 1401.03    5533 1406.15  5570.9 1411.87
#Mann= 5 ,-1 , 0
  4562.7     .05       0  4583.5     .12       0  4703.9     .05       0
  4987.6     .05       0    5011     .05       0
Bank Sta=4987.6,5011
XS Rating Curve= 0 ,0
Exp/Cntr=0.3,0.1

Type RM Length L Ch R = 1 ,74500   ,500,500,500
BEGIN DESCRIPTION:
PECAN CREEK 149.0
END DESCRIPTION:
XS GIS Cut Line= 3
       2794055.7     10294903.09      2793813.46     10295127.19
       2793605.7     10295503.09
#Sta/Elev= 30
    4670 1361.29  4712.3 1359.08    4833 1343.96  4880.2 1340.34  4958.9  1336.2
  4967.4 1337.39  4991.6 1334.51  4992.1 1334.01  5015.1 1334.51  5025.2 1338.69
  5046.9 1342.98  5068.7 1343.79    5150 1352.63  5166.1 1356.69  5187.8 1365.98
  5193.5 1369.94  5209.6 1373.28  5215.3 1377.24  5231.4 1380.72  5237.1 1384.94
  5253.1 1387.84  5258.8 1391.14  5290.9 1395.73  5296.2 1398.36  5312.7 1399.35
  5318.4 1401.51  5334.5    1403    5378 1411.58  5405.9 1415.09  5429.5  1419.6
#Mann= 7 ,-1 , 0
    4670     .05       0  4880.2     .12       0  4958.9     .05       0
  4991.6     .03       0  5015.1     .05       0  5296.2     .12       0
  5405.9     .05       0
Bank Sta=4991.6,5015.1
XS Rating Curve= 0 ,0
Exp/Cntr=0.3,0.1

Type RM Length L Ch R = 1 ,74000   ,500,500,500
BEGIN DESCRIPTION:
PECAN CREEK 148.0
END DESCRIPTION:
XS GIS Cut Line= 3
      2794305.66      10294953.1      2793529.94     10294732.79
      2793455.69     10294553.13
#Sta/Elev= 30
  4193.6 1375.92  4283.5 1370.88  4370.3 1362.75  4429.5 1362.75  4513.6 1353.76
  4614.5 1344.84  4642.4 1344.31  4786.1  1337.2  4817.3 1338.64  4856.7 1335.01
  4859.6 1334.92  4879.7  1332.1  4973.2 1332.98  4982.2 1329.48  4982.7 1328.98
  5005.9 1329.48  5020.1  1331.3  5032.1 1338.68  5051.7 1356.78  5054.8 1360.84
  5086.2 1380.98  5102.6 1384.82    5108 1388.38  5126.5 1389.33  5131.9 1391.68
  5152.2 1394.49  5155.8 1396.38  5179.8 1395.29  5185.2 1397.75  5194.4 1398.09
#Mann= 9 ,-1 , 0
  4193.6     .05       0  4513.6     .12       0  4642.4     .05       0
  4856.7     .12       0  4859.6     .05       0  4982.2     .05       0
  5005.9     .05       0  5051.7     .12       0  5152.2     .05       0
Bank Sta=4982.2,5005.9
XS Rating Curve= 0 ,0
Exp/Cntr=0.3,0.1

Type RM Length L Ch R = 1 ,73500   ,500,500,500
BEGIN DESCRIPTION:
PECAN CREEK 147.0
END DESCRIPTION:
XS GIS Cut Line= 3
      2794055.67     10294853.07      2793977.39     10294588.92
      2793905.67     10294403.08
#Sta/Elev= 30
  4724.5 1359.53  4733.6 1359.01  4807.6 1350.38  4812.8 1349.53  4818.3 1346.85
  4839.2 1345.55  4851.2 1343.45  4870.5 1341.63  4879.3 1339.18  4912.2 1334.64
  4917.7 1332.42  4983.3 1326.34  4983.8 1325.84  5007.1 1326.34  5015.1  1328.2
  5027.7 1328.73  5038.4  1330.3  5045.1 1332.48  5059.8 1334.68  5069.7 1340.66
  5074.5 1345.67  5081.3 1350.24    5092 1353.62  5099.6 1359.85  5113.4 1367.62
  5124.1 1371.36    5135 1377.44    5167 1388.91  5189.5 1395.06  5199.2 1396.15
#Mann= 5 ,-1 , 0
  4724.5     .05       0  4733.6     .12       0  4983.3     .05       0
  5007.1     .12       0  5074.5     .12       0
Bank Sta=4983.3,5007.1
XS Rating Curve= 0 ,0
Exp/Cntr=0.3,0.1

Type RM Length L Ch R = 1 ,73000   ,500,500,500
BEGIN DESCRIPTION:
PECAN CREEK 146.0
END DESCRIPTION:
XS GIS Cut Line= 3
      2794405.68     10294903.14      2794454.71     10294481.88
       2794255.7     10294153.13
#Sta/Elev= 30
  4575.9 1372.13  4615.2 1367.63  4620.2 1368.79  4626.3 1366.51  4650.4 1363.33
  4703.7  1354.9  4708.8 1356.46  4777.3 1345.16  4787.2 1344.16  4797.4 1345.59
  4847.8 1339.09  4908.2 1336.06  4945.6  1331.7  4958.5 1330.74  4964.3 1327.83
  4969.4 1329.76    4985 1321.99  4985.5 1321.49  5008.8 1321.99  5033.6 1327.69
  5048.8  1329.5  5070.1 1328.06  5092.1 1324.36  5122.5 1331.65  5170.6 1337.58
  5240.9 1358.74  5288.5 1373.12  5325.9 1384.15  5339.7 1390.41  5384.3 1400.06
#Mann= 8 ,-1 , 0
  4575.9     .12       0  4650.4     .05       0  4945.6     .12       0
    4985     .07       0  5008.8     .12       0  5170.6     .05       0
  5240.9     .12       0  5288.5     .05       0
Bank Sta=4985,5008.8
XS Rating Curve= 0 ,0
Exp/Cntr=0.3,0.1

Type RM Length L Ch R = 1 ,72500   ,500,500,500
BEGIN DESCRIPTION:
PECAN CREEK 145.0
END DESCRIPTION:
XS GIS Cut Line= 3
      2795155.68     10294503.11      2794892.08     10294255.58
      2794705.69     10294053.11
#Sta/Elev= 30
  4638.4 1358.67  4723.1 1351.93  4815.4 1340.44  4850.6 1334.09  4921.4 1326.04
  4935.6 1326.86  4942.5 1325.93  4949.8 1326.94  4956.6 1325.25  4963.9 1326.76
  4970.8 1325.44  4978.2  1325.6  4992.2  1320.7  5020.3 1321.86  5022.6 1320.37
  5023.1 1319.87  5046.4 1320.37  5062.8 1324.08  5091.2 1326.74  5112.2 1330.78
  5119.5 1334.71  5126.3 1335.93  5147.9 1343.18    5183  1351.5  5204.6 1358.83
  5234.2 1366.62  5261.3 1371.24  5268.1 1370.75  5271.3 1371.86  5275.2 1372.03
#Mann= 6 ,-1 , 0
  4638.4     .05       0  4978.2     .12       0  5022.6     .07       0
  5046.4     .12       0  5234.2     .05       0  5271.3     .12       0
Bank Sta=5022.6,5046.4
XS Rating Curve= 0 ,0
Exp/Cntr=0.3,0.1