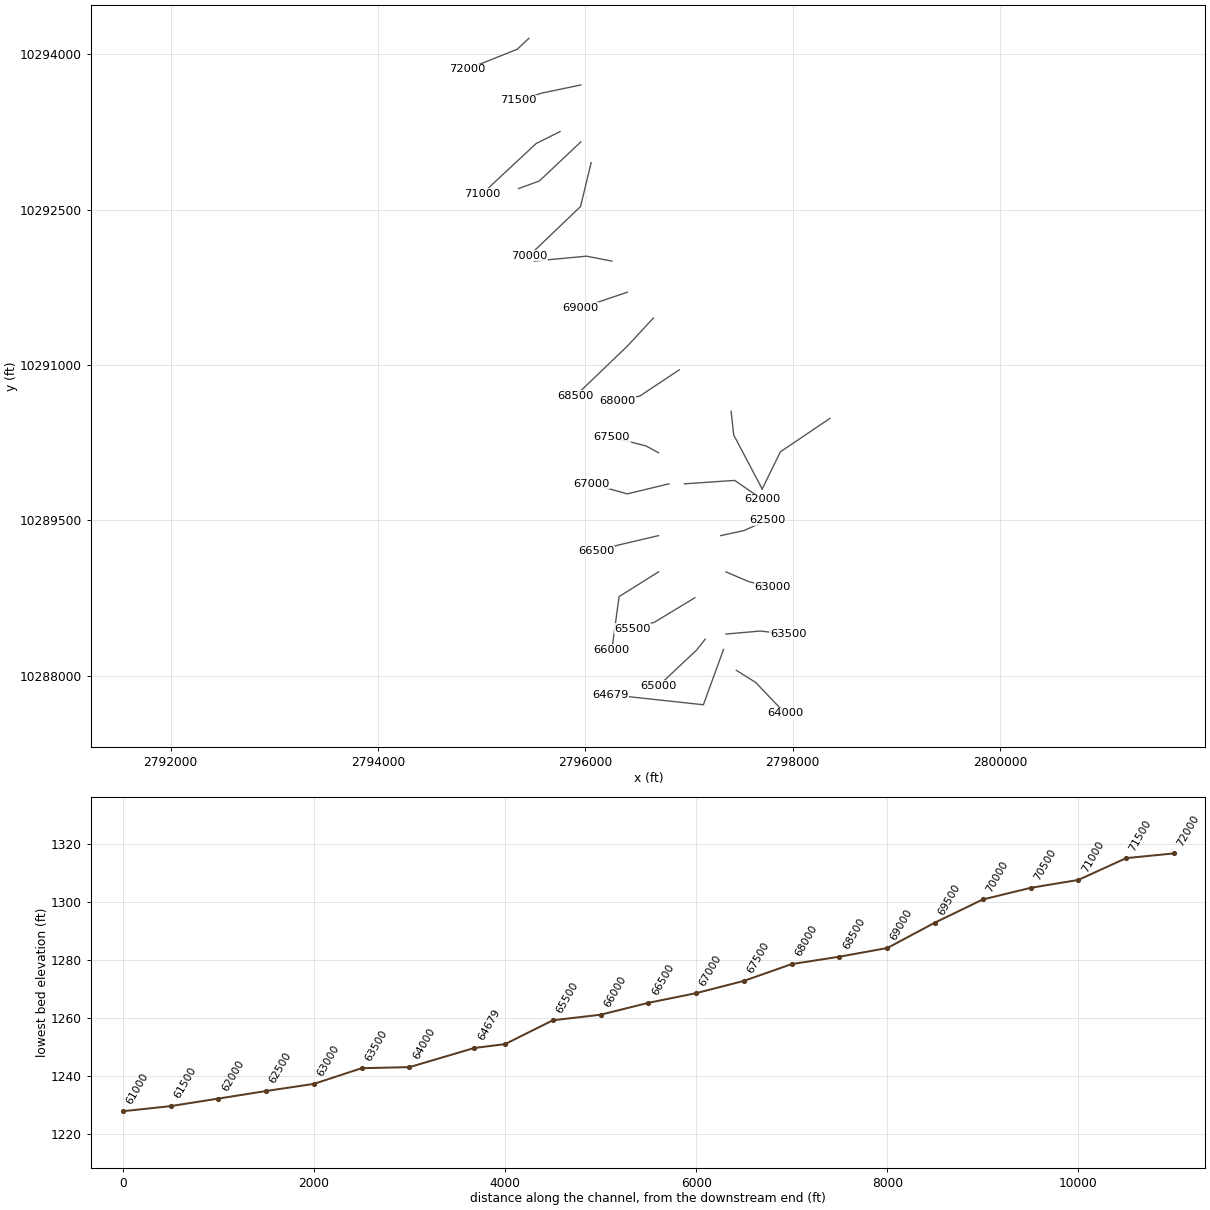
HEC-RAS study PECAN CREEK.prj: PECAN CREEK Base Level Engineering

--- PECAN CREEK.g01 (geometry) --- (continued)

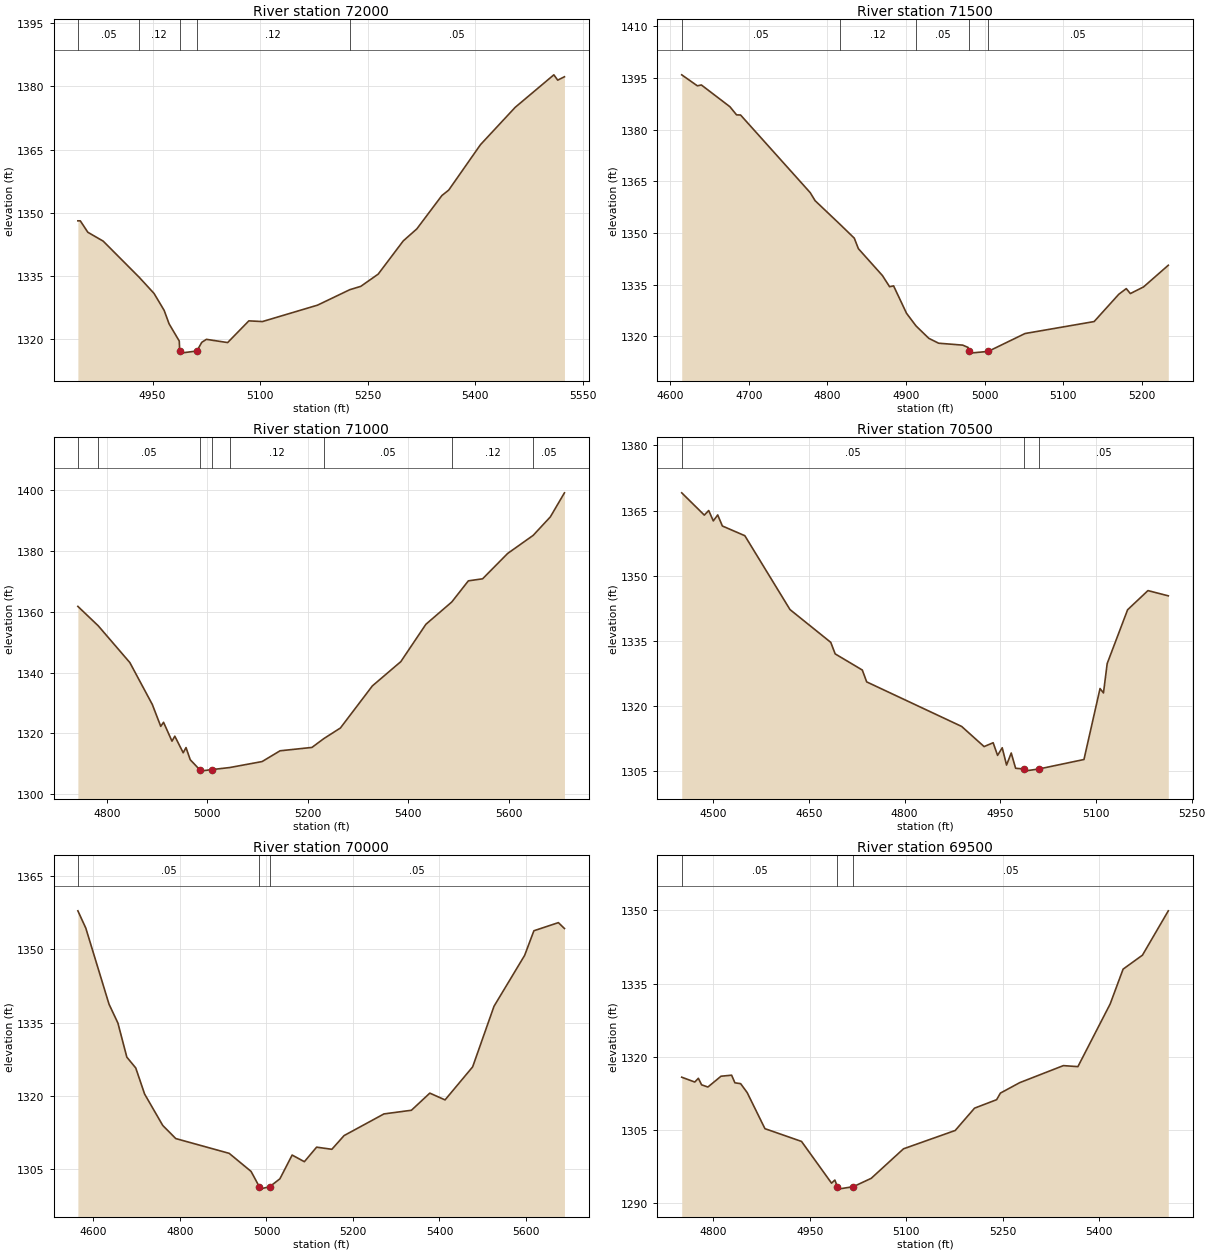
Type RM Length L Ch R = 1 ,72000   ,500,500,500
BEGIN DESCRIPTION:
PECAN CREEK 144.0
END DESCRIPTION:
XS GIS Cut Line= 3
       2795455.7     10294153.13      2795342.91     10294047.83
      2794855.68     10293853.11
#Sta/Elev= 30
  4845.7 1348.12  4849.1 1348.12  4859.6 1345.41  4881.1  1343.3    4931 1334.79
    4952 1330.91  4966.1  1326.9    4973  1323.7  4987.2 1319.62  4987.8 1317.26
  4988.3 1316.76  5011.7 1317.26  5018.6 1319.32  5025.1 1320.03  5054.7 1319.26
  5084.3 1324.41  5103.2 1324.24  5180.1 1328.13  5225.2  1331.8  5240.5 1332.59
  5264.8 1335.49  5299.8 1343.37  5318.7 1346.21  5353.7 1354.12  5363.2 1355.41
  5407.5 1366.17    5456 1375.03  5509.9 1382.73  5515.3 1381.47  5524.7 1382.27
#Mann= 5 ,-1 , 0
  4845.7     .05       0    4931     .12       0  4987.8     .07       0
  5011.7     .12       0  5225.2     .05       0
Bank Sta=4987.8,5011.7
XS Rating Curve= 0 ,0
Exp/Cntr=0.3,0.1

Type RM Length L Ch R = 1 ,71500   ,500,500,500
BEGIN DESCRIPTION:
PECAN CREEK 143.0
END DESCRIPTION:
XS GIS Cut Line= 3
      2795955.67     10293703.11      2795578.35     10293624.13
       2795355.7     10293553.12
#Sta/Elev= 30
  4614.5 1395.88  4634.4 1392.69  4639.5 1392.94  4675.8 1386.63  4684.3 1384.26
  4689.4 1384.22    4778  1361.7  4784.2 1359.37  4816.4  1352.4  4834.1 1348.49
  4839.3 1345.44  4869.9 1337.64    4879  1334.4  4884.1 1334.64  4900.6 1326.68
  4912.7 1323.01  4928.9 1319.43  4941.4 1318.01  4972.1 1317.45  4978.9 1316.78
  4980.5 1315.63    4981 1315.13  5004.5 1315.63  5051.4 1320.82  5139.3 1324.29
  5170.7 1332.21  5180.2 1333.85  5185.4 1332.41  5202.2 1334.34  5233.7 1340.63
#Mann= 5 ,-1 , 0
  4614.5     .05       0  4816.4     .12       0  4912.7     .05       0
  4980.5     .05       0  5004.5     .05       0
Bank Sta=4980.5,5004.5
XS Rating Curve= 0 ,0
Exp/Cntr=0.3,0.1

Type RM Length L Ch R = 1 ,71000   ,500,500,500
BEGIN DESCRIPTION:
PECAN CREEK 142.0
END DESCRIPTION:
XS GIS Cut Line= 3
      2795755.68     10293253.11      2795525.34     10293137.99
      2795005.71     10292653.14
#Sta/Elev= 30
  4742.5 1361.82  4783.1 1355.42  4845.9 1343.34  4890.6 1329.56  4907.4 1322.35
    4913 1323.68  4929.8 1317.48  4935.4 1319.12  4952.1 1313.66  4957.7 1315.37
  4966.1 1311.37  4984.8 1308.12  4985.3 1307.62  5008.9 1308.12  5044.7  1308.8
  5109.1 1310.77  5144.8 1314.31  5208.3 1315.42  5231.8 1318.31  5264.9 1321.81
  5328.5 1335.66  5385.1 1343.64    5435 1355.93  5486.5 1363.27  5519.5 1370.22
  5547.8 1370.89  5597.6 1379.22  5648.5 1385.19  5682.6 1391.26  5710.7 1399.18
#Mann= 8 ,-1 , 0
  4742.5     .12       0  4783.1     .05       0  4984.8     .05       0
  5008.9     .05       0  5044.7     .12       0  5231.8     .05       0
  5486.5     .12       0  5648.5     .05       0
Bank Sta=4984.8,5008.9
XS Rating Curve= 0 ,0
Exp/Cntr=0.3,0.1

Type RM Length L Ch R = 1 ,70500   ,500,500,500
BEGIN DESCRIPTION:
PECAN CREEK 141.0
END DESCRIPTION:
XS GIS Cut Line= 3
      2795955.67      10293153.1       2795556.1     10292776.18
       2795355.7     10292703.12
#Sta/Elev= 30
  4450.7 1369.08  4486.1 1363.94    4493    1365  4500.2  1362.6  4507.1 1363.98
  4514.4 1361.43  4549.6 1359.19  4620.4 1342.15  4684.3 1334.59  4691.2 1331.93
  4733.7 1328.21  4740.6 1325.47  4889.4  1315.2  4924.6 1310.55  4938.8 1311.44
  4945.7 1308.52    4953 1310.28  4959.8 1306.29  4967.1 1309.07    4974 1305.55
  4986.5 1305.39    4987 1304.89  5010.6 1305.39  5081.1 1307.57  5106.3 1323.94
  5111.7 1322.93  5117.5  1329.7  5149.5 1342.11  5181.4 1346.53  5213.3 1345.32
#Mann= 3 ,-1 , 0
  4450.7     .05       0  4986.5     .05       0  5010.6     .05       0
Bank Sta=4986.5,5010.6
XS Rating Curve= 0 ,0
Exp/Cntr=0.3,0.1

Type RM Length L Ch R = 1 ,70000   ,500,500,500
BEGIN DESCRIPTION:
PECAN CREEK 140.0
END DESCRIPTION:
XS GIS Cut Line= 3
      2796055.69     10292953.13      2795953.36     10292529.41
      2795455.66     10292053.09
#Sta/Elev= 30
  4564.1 1357.91  4582.5 1354.36  4636.1 1338.79  4656.7 1334.91  4677.3 1327.93
  4697.9 1325.72  4718.4 1320.37  4760.3 1313.94  4790.4 1311.25  4913.9 1308.22
  4964.5 1304.52  4983.5 1301.39    4984 1300.89  5007.6 1301.39  5031.1    1303
  5059.4 1307.87  5087.7 1306.51    5116 1309.49  5151.2 1309.05  5179.5 1311.86
  5271.7  1316.3  5335.2 1317.05  5377.7 1320.56  5412.9 1319.17  5476.7 1325.94
  5526.1 1338.36  5596.9 1348.79  5618.3 1353.83  5674.9 1355.49  5688.9 1354.29
#Mann= 3 ,-1 , 0
  4564.1     .05       0  4983.5     .05       0  5007.6     .05       0
Bank Sta=4983.5,5007.6
XS Rating Curve= 0 ,0
Exp/Cntr=0.3,0.1

Type RM Length L Ch R = 1 ,69500   ,500,500,500
BEGIN DESCRIPTION:
PECAN CREEK 139.0
END DESCRIPTION:
XS GIS Cut Line= 3
      2796255.65     10292003.12      2796010.99     10292050.46
       2795505.7     10292003.11
#Sta/Elev= 30
  4750.8 1315.83  4771.1 1314.84  4776.7 1315.61  4781.7 1314.27  4791.5 1313.82
  4811.9 1316.03  4828.4 1316.24  4833.5 1314.68  4842.4 1314.51  4852.6 1312.68
  4880.2  1305.3  4937.1 1302.69  4983.8 1294.15  4988.9 1294.79    4993 1293.43
  4993.5 1292.93  5017.6 1293.43  5045.5 1295.14  5095.7 1301.18  5176.1 1304.93
  5206.2  1309.5  5240.5 1311.23  5246.4 1312.58  5276.5 1314.72  5344.3  1318.2
  5366.9 1317.99  5417.1 1330.82  5437.2 1337.94  5467.3  1340.8  5507.5 1349.87
#Mann= 3 ,-1 , 0
  4750.8     .05       0    4993     .05       0  5017.6     .05       0
Bank Sta=4993,5017.6
XS Rating Curve= 0 ,0
Exp/Cntr=0.3,0.1

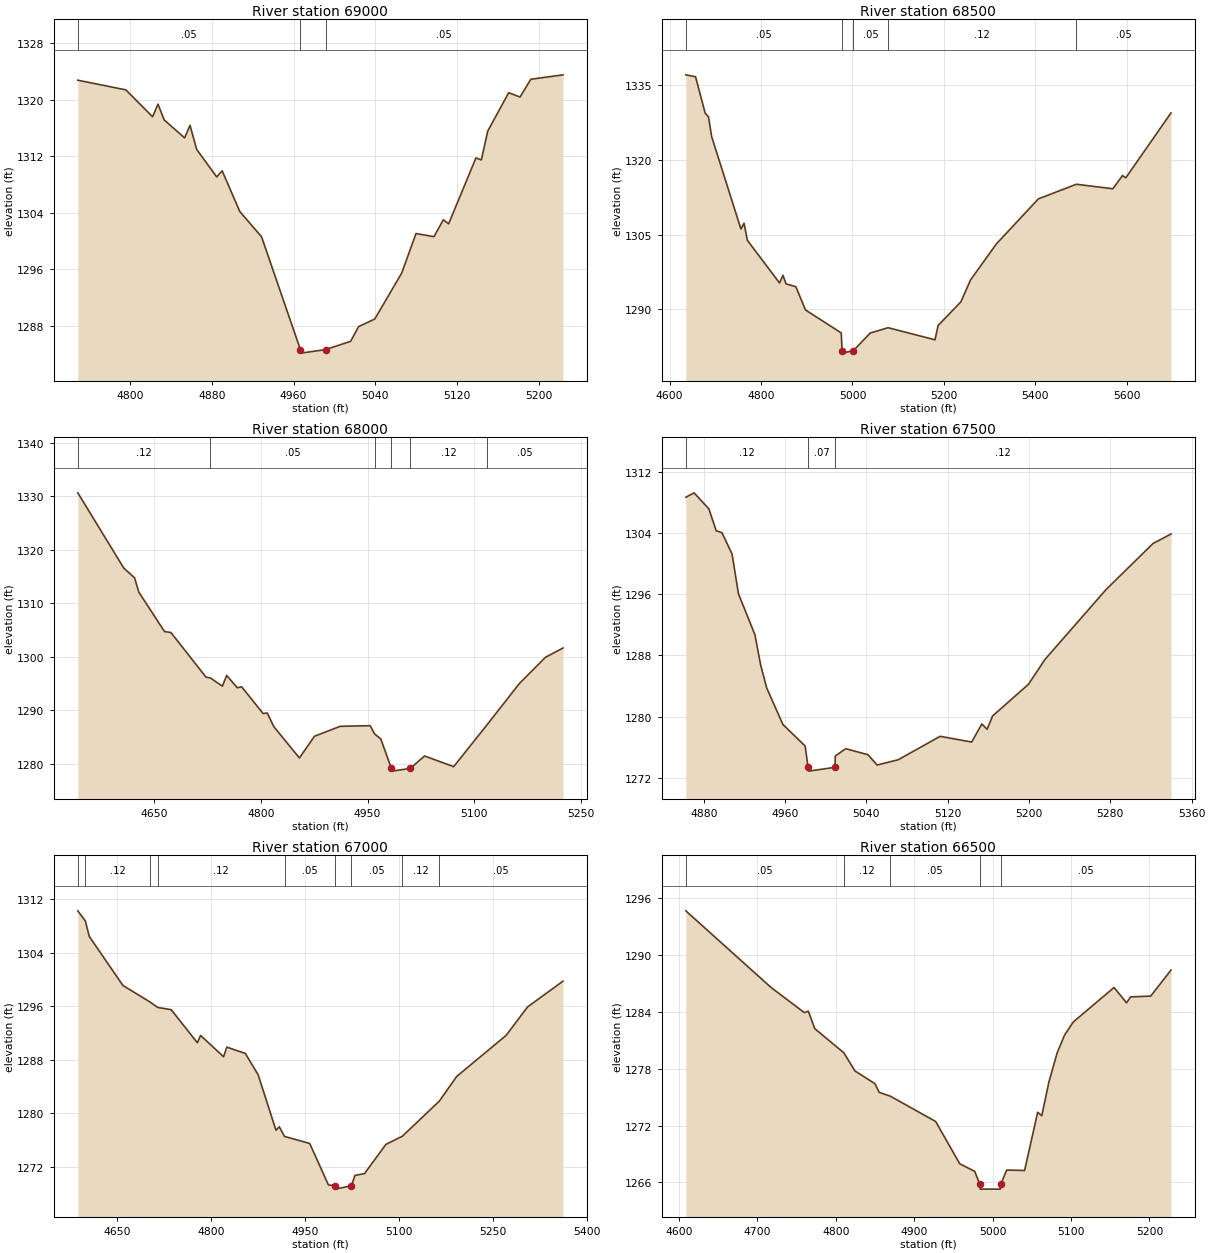
Type RM Length L Ch R = 1 ,69000   ,500,500,500
BEGIN DESCRIPTION:
PECAN CREEK 138.0
END DESCRIPTION:
XS GIS Cut Line= 3
      2796405.67     10291703.11      2796168.17     10291622.21
      2795955.72     10291553.12
#Sta/Elev= 30
  4749.1 1322.78  4796.1 1321.41  4822.2 1317.61  4827.5 1319.39  4833.6 1317.15
  4853.5 1314.62  4858.8  1316.4  4865.3 1312.99  4884.9 1309.09  4890.2 1309.96
  4907.5 1304.19  4928.7 1300.63  4966.7 1284.66  4967.2 1284.16  4991.3 1284.66
  5015.8 1285.83  5023.6 1287.91  5039.4 1288.99  5065.7 1295.48  5079.7 1301.08
  5097.3 1300.64  5106.4 1303.03  5111.6 1302.46  5138.3 1311.78  5143.6  1311.5
  5149.8 1315.57  5170.3 1321.01  5181.4  1320.4  5191.9 1322.91  5223.4 1323.54
#Mann= 3 ,-1 , 0
  4749.1     .05       0  4966.7     .05       0  4991.3     .05       0
Bank Sta=4966.7,4991.3
XS Rating Curve= 0 ,0
Exp/Cntr=0.3,0.1

Type RM Length L Ch R = 1 ,68500   ,500,500,500
BEGIN DESCRIPTION:
PECAN CREEK 137.0
END DESCRIPTION:
XS GIS Cut Line= 3
      2796655.69     10291453.12      2796408.34     10291185.52
      2795905.68     10290703.11
#Sta/Elev= 30
  4635.6 1337.12  4656.9 1336.74  4677.9 1329.44  4685.2 1328.68    4692 1324.74
  4756.1 1306.14  4762.9  1307.3  4770.3 1303.85  4840.6 1295.29    4848 1296.84
  4854.8 1295.11  4876.3 1294.54  4897.3 1289.87  4975.5 1285.25  4977.4 1281.69
  4977.9 1281.19    5002 1281.69    5039 1285.23  5077.9  1286.3  5180.5 1283.87
  5187.4 1286.75  5237.1 1291.49  5258.2 1295.89  5314.8 1303.14  5406.6 1312.19
  5489.8 1315.13  5569.5 1314.22  5590.6 1316.88  5597.8 1316.42  5696.7 1329.47
#Mann= 5 ,-1 , 0
  4635.6     .05       0  4977.4     .05       0    5002     .05       0
  5077.9     .12       0  5489.8     .05       0
Bank Sta=4977.4,5002
XS Rating Curve= 0 ,0
Exp/Cntr=0.3,0.1

Type RM Length L Ch R = 1 ,68000   ,500,500,500
BEGIN DESCRIPTION:
PECAN CREEK 136.0
END DESCRIPTION:
XS GIS Cut Line= 3
      2796905.68     10290953.11        2796525.     10290700.44
      2796305.65      10290653.1
#Sta/Elev= 30
  4543.1 1330.68  4607.7  1316.6  4622.8 1314.79  4628.8  1312.1  4664.9 1304.73
  4673.9 1304.55  4723.1 1296.21  4729.3 1296.06  4746.1 1294.52  4752.1 1296.53
  4767.1 1294.22  4773.1 1294.42  4803.2 1289.41  4809.2 1289.49  4818.3 1286.95
  4854.3 1281.09  4875.4 1285.15  4911.5 1287.01  4953.6 1287.13  4959.8 1285.59
  4968.6 1284.64  4983.4 1279.13  4983.9 1278.63  5009.8 1279.13    5030 1281.46
  5070.9 1279.47  5118.3 1287.39    5163 1294.99  5199.7 1299.91  5224.4 1301.66
#Mann= 6 ,-1 , 0
  4543.1     .12       0  4729.3     .05       0  4959.8     .12       0
  4983.4     .07       0  5009.8     .12       0  5118.3     .05       0
Bank Sta=4983.4,5009.8
XS Rating Curve= 0 ,0
Exp/Cntr=0.3,0.1

Type RM Length L Ch R = 1 ,67500   ,500,500,500
BEGIN DESCRIPTION:
PECAN CREEK 135.0
END DESCRIPTION:
XS GIS Cut Line= 3
      2796705.67     10290153.12      2796584.74     10290218.76
      2796255.68     10290303.11
#Sta/Elev= 30
  4862.4 1308.73  4870.5 1309.31  4885.1 1307.21  4892.3 1304.34    4898 1304.08
  4907.9 1301.29  4914.2 1296.08  4930.4 1290.72    4936 1286.76    4942 1283.74
  4957.9 1278.96  4979.8 1276.14  4982.7 1273.35  4983.2 1272.85  5009.2 1273.35
  5009.4 1274.83  5019.7 1275.79  5041.6    1275  5050.6 1273.65  5071.3 1274.34
  5112.6 1277.41  5143.6 1276.66  5153.6 1279.03  5158.8 1278.33  5164.2 1280.08
  5199.5 1284.23  5215.8  1287.5  5275.9 1296.65  5321.9 1302.66  5339.7 1303.92
#Mann= 3 ,-1 , 0
  4862.4     .12       0  4982.7     .07       0  5009.2     .12       0
Bank Sta=4982.7,5009.2
XS Rating Curve= 0 ,0
Exp/Cntr=0.3,0.1

Type RM Length L Ch R = 1 ,67000   ,500,500,500
BEGIN DESCRIPTION:
PECAN CREEK 134.0
END DESCRIPTION:
XS GIS Cut Line= 3
      2796805.67     10289853.11      2796404.52     10289756.16
      2796055.64     10289853.12
#Sta/Elev= 30
  4587.3 1310.29  4599.4 1308.77  4605.6 1306.46  4659.3 1299.12  4701.9 1296.68
    4715 1295.82  4736.4 1295.49  4778.2 1290.54  4783.4 1291.63  4820.1 1288.44
  4825.2 1289.88  4854.8 1288.94  4875.3 1285.74  4903.8 1277.43    4909 1277.96
  4917.4 1276.51  4957.6 1275.46  4987.5 1269.25  4997.5 1269.12    4998 1268.62
  5024.1 1269.12  5029.9 1270.67  5045.1 1270.94  5079.3 1275.32  5105.6 1276.54
  5164.6  1281.8  5192.4  1285.5  5271.3 1291.64  5305.5  1295.9  5362.1 1299.76
#Mann= 9 ,-1 , 0
  4587.3     .05       0  4599.4     .12       0  4701.9     .05       0
    4715     .12       0  4917.4     .05       0  4997.5     .05       0
  5024.1     .05       0  5105.6     .12       0  5164.6     .05       0
Bank Sta=4997.5,5024.1
XS Rating Curve= 0 ,0
Exp/Cntr=0.3,0.1

Type RM Length L Ch R = 1 ,66500   ,500,500,500
BEGIN DESCRIPTION:
PECAN CREEK 133.0
END DESCRIPTION:
XS GIS Cut Line= 3
      2796705.71     10289353.12      2796324.96     10289263.74
      2796105.69     10289203.11
#Sta/Elev= 30
  4608.9 1294.66  4717.6 1286.57    4760 1283.92  4765.1 1284.07  4773.3 1282.23
  4810.3 1279.68  4824.6 1277.76    4850 1276.42  4855.5  1275.5  4869.6  1275.1
  4927.4 1272.43  4958.2 1267.96  4977.2 1267.17  4983.8 1265.79  4984.3 1265.29
  5009.9 1265.29  5010.4 1265.79    5018  1267.3  5040.8 1267.26  5057.5  1273.4
  5062.7 1273.04  5071.9 1276.62  5082.3 1279.66  5091.8 1281.55    5103 1282.94
  5154.9 1286.57  5170.8 1284.95    5176 1285.58  5201.6 1285.66  5227.5 1288.41
#Mann= 5 ,-1 , 0
  4608.9     .05       0  4810.3     .12       0  4869.6     .05       0
  4983.8     .03       0  5010.4     .05       0
Bank Sta=4983.8,5010.4
XS Rating Curve= 0 ,0
Exp/Cntr=0.3,0.1

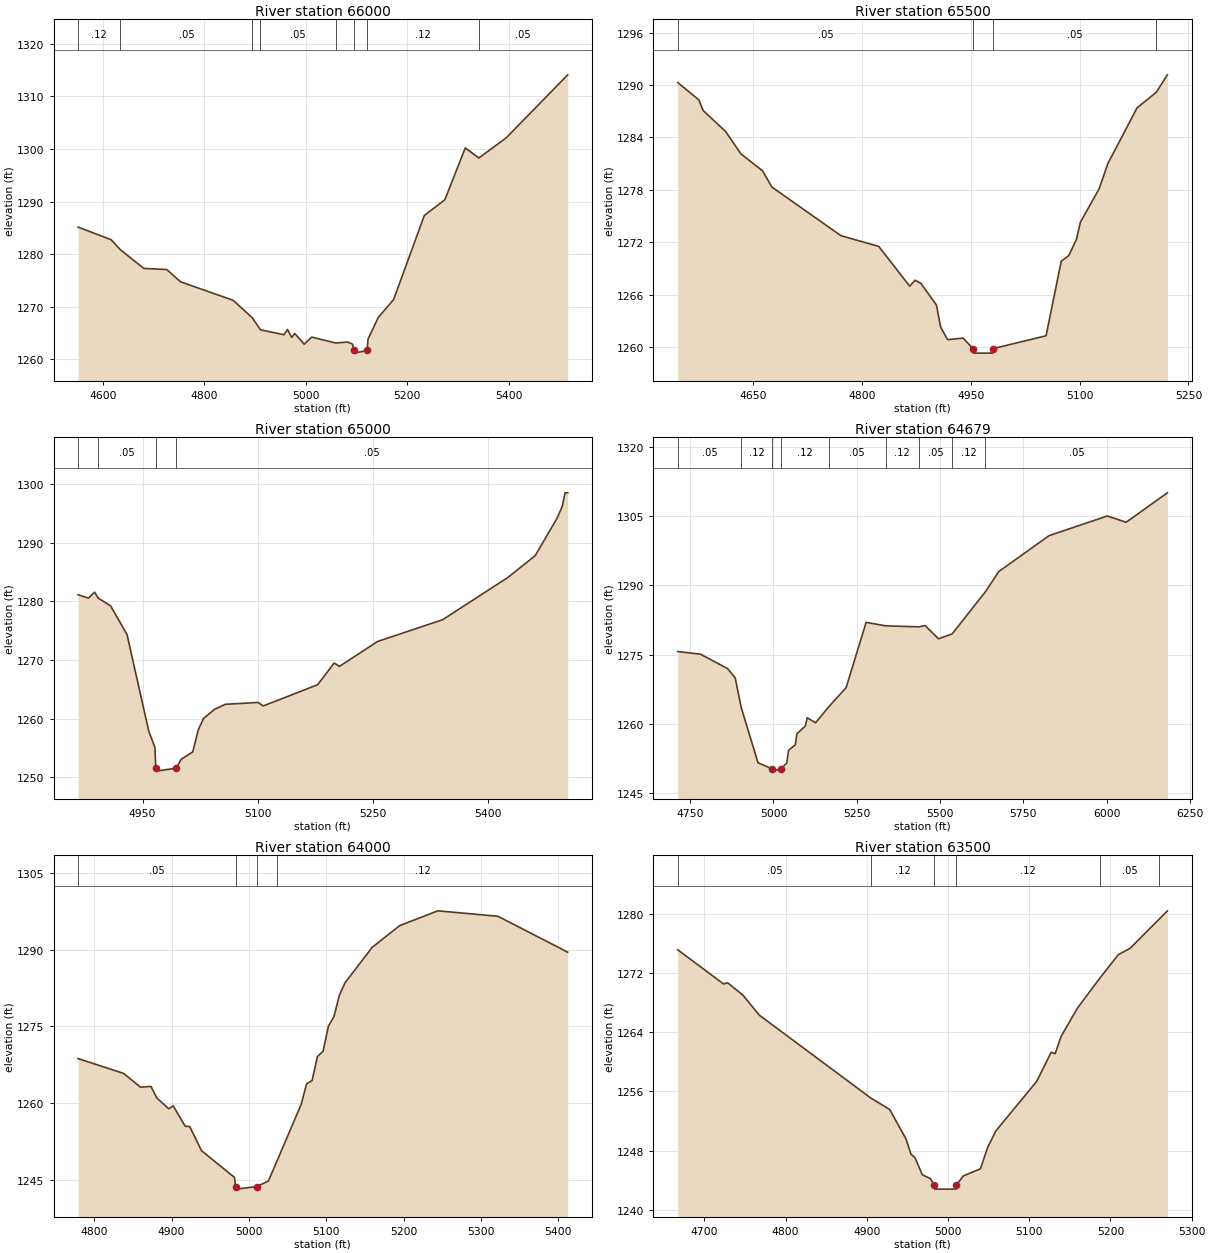
Type RM Length L Ch R = 1 ,66000   ,500,500,500
BEGIN DESCRIPTION:
PECAN CREEK 132.0
END DESCRIPTION:
XS GIS Cut Line= 3
      2796705.68     10289003.11      2796325.21     10288764.69
      2796255.68      10288253.1
#Sta/Elev= 30
    4551 1285.16  4616.4 1282.74  4634.5 1280.84  4680.8 1277.29    4726 1277.08
  4753.1 1274.75  4856.8 1271.23  4894.8 1267.88  4910.7 1265.62    4957 1264.69
    4964 1265.69  4972.3 1264.17  4978.2 1264.93  4996.8 1262.89  5011.7 1264.24
  5058.6 1263.12  5082.3  1263.3  5092.4 1262.88  5094.4 1261.69  5094.9 1261.19
    5121 1261.69  5122.7 1263.87  5142.9 1267.97  5173.2 1271.38  5233.7 1287.36
  5274.1 1290.33  5314.4 1300.19  5341.3 1298.29  5395.2 1302.12  5516.3 1314.09
#Mann= 8 ,-1 , 0
    4551     .12       0  4634.5     .05       0  4894.8     .12       0
  4910.7     .05       0  5058.6     .12       0  5094.4     .05       0
    5121     .12       0  5341.3     .05       0
Bank Sta=5094.4,5121
XS Rating Curve= 0 ,0
Exp/Cntr=0.3,0.1

Type RM Length L Ch R = 1 ,65500   ,500,500,500
BEGIN DESCRIPTION:
PECAN CREEK 131.0
END DESCRIPTION:
XS GIS Cut Line= 3
      2797055.71     10288753.13      2796666.98     10288517.63
      2796455.71     10288453.12
#Sta/Elev= 30
  4545.5  1290.3  4574.6 1288.31  4580.6 1287.09  4611.5 1284.69  4632.8 1282.11
  4662.5 1280.18  4675.5 1278.31  4770.5 1272.75  4822.8 1271.51  4865.5 1266.95
  4872.9 1267.64    4881 1267.27  4902.4 1264.79  4908.2 1262.25  4917.8 1260.82
  4939.2    1261    4953 1259.78  4953.5 1259.28  4979.3 1259.28  4979.8 1259.78
  5053.6 1261.27  5074.5 1269.81    5085 1270.47  5095.5 1272.34  5100.9 1274.28
  5126.8 1278.12  5138.9 1281.02  5179.1  1287.4  5205.4 1289.16  5220.9 1291.18
#Mann= 4 ,-1 , 0
  4545.5     .05       0    4953     .03       0  4979.8     .05       0
  5205.4     .12       0
Bank Sta=4953,4979.8
XS Rating Curve= 0 ,0
Exp/Cntr=0.3,0.1

Type RM Length L Ch R = 1 ,65000   ,321,321,321
BEGIN DESCRIPTION:
PECAN CREEK 130.0
END DESCRIPTION:
XS GIS Cut Line= 3
      2797155.68      10288353.1      2797072.47     10288248.07
      2796705.69     10287903.12
#Sta/Elev= 30
    4866 1281.15  4879.6 1280.58  4887.6 1281.58  4892.2 1280.58  4908.4 1279.25
  4929.8 1274.36  4958.1 1257.88  4966.2 1255.06  4967.2 1251.56  4967.7 1251.06
    4994 1251.56    5000 1253.04  5015.4 1254.35  5022.7 1258.16  5029.5 1260.06
  5043.7 1261.59  5057.8 1262.46  5100.3 1262.77  5107.2 1262.18    5178  1265.8
  5199.5  1269.5  5206.3 1268.93  5256.1 1273.18  5340.7 1276.89  5425.6 1284.09
  5461.2 1287.81  5489.6 1294.18  5496.4 1296.21  5500.1 1298.53  5503.5 1298.53
#Mann= 4 ,-1 , 0
    4866     .12       0  4892.2     .05       0  4967.2     .05       0
    4994     .05       0
Bank Sta=4967.2,4994
XS Rating Curve= 0 ,0
Exp/Cntr=0.3,0.1

Type RM Length L Ch R = 1 ,64679   ,679,679,679
BEGIN DESCRIPTION:
Mapping XS 37a18cbe
END DESCRIPTION:
XS GIS Cut Line= 3
      2797332.86     10288255.18      2797138.42     10287720.46
      2796242.56     10287817.68
#Sta/Elev= 30
  4712.6 1275.66  4780.7 1275.09  4861.9 1271.99  4885.1 1269.98  4903.1 1263.58
  4953.6 1251.56  4996.1 1250.24  4996.6 1249.74  5022.9 1250.24  5040.1 1251.51
  5045.4 1254.26  5065.4 1255.43  5070.7 1257.86    5096 1259.53  5101.3  1261.3
  5126.6 1260.22  5166.2  1263.7  5218.3 1267.85  5278.3 1281.99  5336.8 1281.23
  5436.6 1281.01  5455.3 1281.29  5495.6 1278.42  5536.5 1279.48  5636.3 1288.61
  5676.6    1293  5827.5 1300.78  6002.4 1305.04  6058.9 1303.68  6182.7 1310.06
#Mann= 9 ,-1 , 0
  4712.6     .05       0  4903.1     .12       0  4996.1     .07       0
  5022.9     .12       0  5166.2     .05       0  5336.8     .12       0
  5436.6     .05       0  5536.5     .12       0  5636.3     .05       0
Bank Sta=4996.1,5022.9
XS Rating Curve= 0 ,0
Exp/Cntr=0.3,0.1

Type RM Length L Ch R = 1 ,64000   ,500,500,500
BEGIN DESCRIPTION:
PECAN CREEK 128.0
END DESCRIPTION:
XS GIS Cut Line= 3
      2797455.72     10288053.09      2797642.96     10287935.88
       2797927.1      10287637.4
#Sta/Elev= 30
  4779.1  1268.7    4838 1265.79  4859.8  1263.1  4873.4 1263.24    4881 1260.98
  4896.3 1258.87  4902.2 1259.42  4917.6 1255.46  4923.5 1255.38  4938.8 1250.66
  4981.2 1245.45  4983.1 1243.64  4983.6 1243.14  5009.9 1243.64  5025.1 1244.71
  5036.7 1248.77  5067.6 1259.74  5074.5 1263.72  5081.7 1264.41  5088.6 1269.09
  5095.9 1270.14  5102.8 1275.04    5110 1276.94  5116.9 1281.06  5124.2 1283.52
  5159.4 1290.47    5195 1294.72  5244.3 1297.61    5322 1296.54  5412.1 1289.52
#Mann= 4 ,-1 , 0
  4779.1     .05       0  4983.1     .05       0  5009.9     .05       0
  5036.7     .12       0
Bank Sta=4983.1,5009.9
XS Rating Curve= 0 ,0
Exp/Cntr=0.3,0.1

Type RM Length L Ch R = 1 ,63500   ,500,500,500
BEGIN DESCRIPTION:
PECAN CREEK 127.0
END DESCRIPTION:
XS GIS Cut Line= 3
      2797355.71     10288403.11      2797687.15     10288431.98
       2797955.7     10288403.11
#Sta/Elev= 30
  4667.3 1275.16  4723.7 1270.54  4728.7  1270.7  4747.6 1269.02  4767.7 1266.32
  4905.2 1255.09  4928.3 1253.55  4948.3 1249.58  4954.4 1247.52  4959.4 1247.04
  4968.4 1244.72  4978.5 1244.19  4983.3 1243.28  4983.8 1242.78  5009.7 1242.78
  5010.2 1243.28  5018.6 1244.55    5040 1245.53  5048.8  1248.4  5058.9 1250.65
  5109.2 1257.35    5127 1261.29    5132 1261.11  5139.3 1263.45  5159.4 1267.27
  5186.9 1271.31  5209.7  1274.5  5224.1 1275.35  5259.9  1279.3  5270.1 1280.43
#Mann= 6 ,-1 , 0
  4667.3     .05       0  4905.2     .12       0  4983.3     .07       0
  5010.2     .12       0  5186.9     .05       0  5259.9     .12       0
Bank Sta=4983.3,5010.2
XS Rating Curve= 0 ,0
Exp/Cntr=0.3,0.1

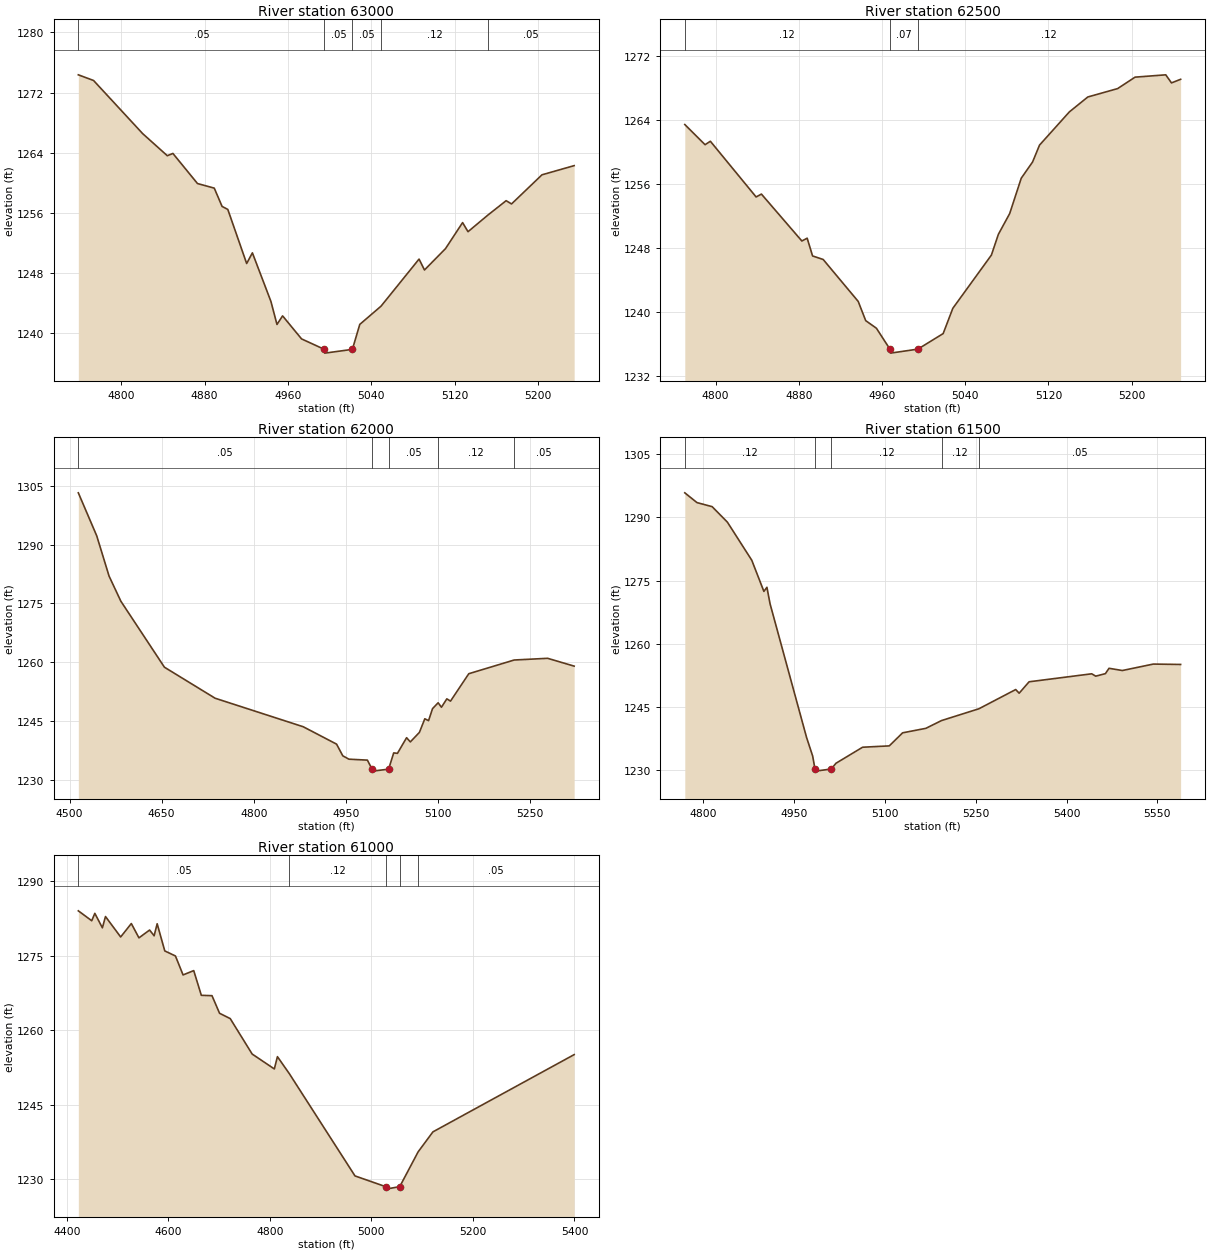
Type RM Length L Ch R = 1 ,63000   ,500,500,500
BEGIN DESCRIPTION:
PECAN CREEK 126.0
END DESCRIPTION:
XS GIS Cut Line= 3
      2797355.65     10289003.13      2797577.48     10288908.41
      2797805.67     10288853.11
#Sta/Elev= 30
  4758.8 1274.36  4773.4 1273.61  4820.6 1266.54  4844.2 1263.61  4849.6 1263.91
  4873.2 1259.91  4889.3  1259.3  4896.8 1256.87  4902.3 1256.47  4920.4 1249.28
  4925.9  1250.7  4943.7 1244.24  4949.5 1241.18  4954.9 1242.32  4973.1 1239.26
    4995 1237.87  4995.5 1237.37  5021.9 1237.87    5029 1241.19  5049.4 1243.61
  5085.9 1249.87  5091.1 1248.42  5111.3 1251.26  5127.7 1254.72  5132.9 1253.51
  5152.1 1255.73  5169.5 1257.63  5174.7  1257.2  5203.9 1261.07  5234.8 1262.29
#Mann= 5 ,-1 , 0
  4758.8     .05       0    4995     .05       0  5021.9     .05       0
  5049.4     .12       0  5152.1     .05       0
Bank Sta=4995,5021.9
XS Rating Curve= 0 ,0
Exp/Cntr=0.3,0.1

Type RM Length L Ch R = 1 ,62500   ,500,500,500
BEGIN DESCRIPTION:
PECAN CREEK 125.0
END DESCRIPTION:
XS GIS Cut Line= 3
      2797305.64      10289353.1      2797530.09     10289401.93
      2797755.64     10289503.09
#Sta/Elev= 30
  4770.3 1263.48  4789.8 1260.96  4794.9 1261.39  4838.9 1254.43    4844 1254.79
  4882.9 1248.93    4888 1249.28  4893.2 1247.06  4903.4 1246.62  4937.1 1241.38
  4944.3 1238.98  4954.6 1238.03  4967.6 1235.42  4968.1 1234.92  4994.5 1235.42
  5018.8 1237.36  5028.1 1240.52  5065.2 1247.17  5071.9 1249.76  5082.8 1252.36
  5093.9 1256.77  5104.8  1258.8  5111.5 1260.91  5140.2 1265.06  5157.9 1266.92
  5186.6 1267.97  5203.4  1269.4  5232.9 1269.69  5238.4 1268.68  5247.2 1269.13
#Mann= 3 ,-1 , 0
  4770.3     .12       0  4967.6     .07       0  4994.5     .12       0
Bank Sta=4967.6,4994.5
XS Rating Curve= 0 ,0
Exp/Cntr=0.3,0.1

Type RM Length L Ch R = 1 ,62000   ,500,500,500
BEGIN DESCRIPTION:
PECAN CREEK 124.0
END DESCRIPTION:
XS GIS Cut Line= 3
      2796955.72     10289853.11       2797440.4     10289886.18
      2797705.66     10289703.13
#Sta/Elev= 30
  4514.2 1303.16  4544.2 1292.21  4564.3 1281.96  4583.5 1275.57  4654.5 1258.77
  4737.1 1250.87  4880.7 1243.61  4935.1 1239.18  4945.2 1236.21  4955.2 1235.35
  4985.3 1235.11    4993 1232.81  4993.5 1232.31  5019.9 1232.81  5028.2 1236.95
  5034.3 1236.84  5049.2 1240.82  5055.3 1239.75  5070.1 1242.17  5078.9 1245.64
    5085 1245.16  5091.5 1248.22  5100.6 1249.71    5106 1248.57  5114.8 1250.71
  5120.8 1250.13  5150.6 1257.11  5224.6  1260.6  5279.1 1261.03  5322.3 1259.04
#Mann= 5 ,-1 , 0
  4514.2     .05       0    4993     .05       0  5019.9     .05       0
  5100.6     .12       0  5224.6     .05       0
Bank Sta=4993,5019.9
XS Rating Curve= 0 ,0
Exp/Cntr=0.3,0.1

Type RM Length L Ch R = 1 ,61500   ,500,500,500
BEGIN DESCRIPTION:
PECAN CREEK 123.0
END DESCRIPTION:
XS GIS Cut Line= 3
      2797405.68     10290553.11      2797431.21     10290323.72
      2797705.67     10289803.14
#Sta/Elev= 30
  4769.2 1295.85  4789.3 1293.53  4814.4 1292.56  4839.6 1288.88  4879.9 1279.82
  4899.9 1272.42  4904.9  1273.4  4910.1 1269.47  4970.4 1237.72  4980.5 1233.29
  4984.3 1230.21  4984.8 1229.71  5011.2 1230.21    5019 1231.58    5063 1235.39
  5107.1 1235.71  5129.1 1238.81  5167.5 1239.88  5193.5 1241.73  5255.2 1244.53
    5316  1249.1  5321.7 1248.23  5338.1 1250.94  5441.6 1252.84  5448.2 1252.28
  5464.2 1252.88  5470.2 1254.15  5492.2 1253.62  5543.3 1255.15  5588.5 1255.06
#Mann= 5 ,-1 , 0
  4769.2     .12       0  4984.3     .07       0  5011.2     .12       0
  5193.5     .12       0  5255.2     .05       0
Bank Sta=4984.3,5011.2
XS Rating Curve= 0 ,0
Exp/Cntr=0.3,0.1

Type RM Length L Ch R = 1 ,61000   ,500,500,500
BEGIN DESCRIPTION:
PECAN CREEK 122.0
END DESCRIPTION:
XS GIS Cut Line= 3
      2798359.46     10290485.02      2797881.01     10290161.97
      2797705.68     10289803.11
#Sta/Elev= 30
  4422.7 1284.04  4449.1 1282.04  4455.2 1283.53  4470.1 1280.62  4476.2 1282.89
  4506.1 1278.77  4527.1 1281.48  4542.1 1278.59  4563.1 1280.17    4572 1279.01
    4578 1281.43    4593 1275.96    4614 1274.94    4629 1271.12    4650 1271.99
    4665 1267.01    4686 1266.94  4700.9 1263.39  4721.9 1262.32  4765.1 1255.18
  4808.8 1252.17  4814.9 1254.65  4838.4 1251.21  4967.7 1230.61  5028.1 1228.45
  5028.6 1227.95  5055.8 1228.45  5092.1 1235.47  5121.2 1239.49  5399.4 1255.06
#Mann= 5 ,-1 , 0
  4422.7     .05       0  4838.4     .12       0  5028.1     .07       0
  5055.8     .12       0  5092.1     .05       0
Bank Sta=5028.1,5055.8
XS Rating Curve= 0 ,0
Exp/Cntr=0.3,0.1