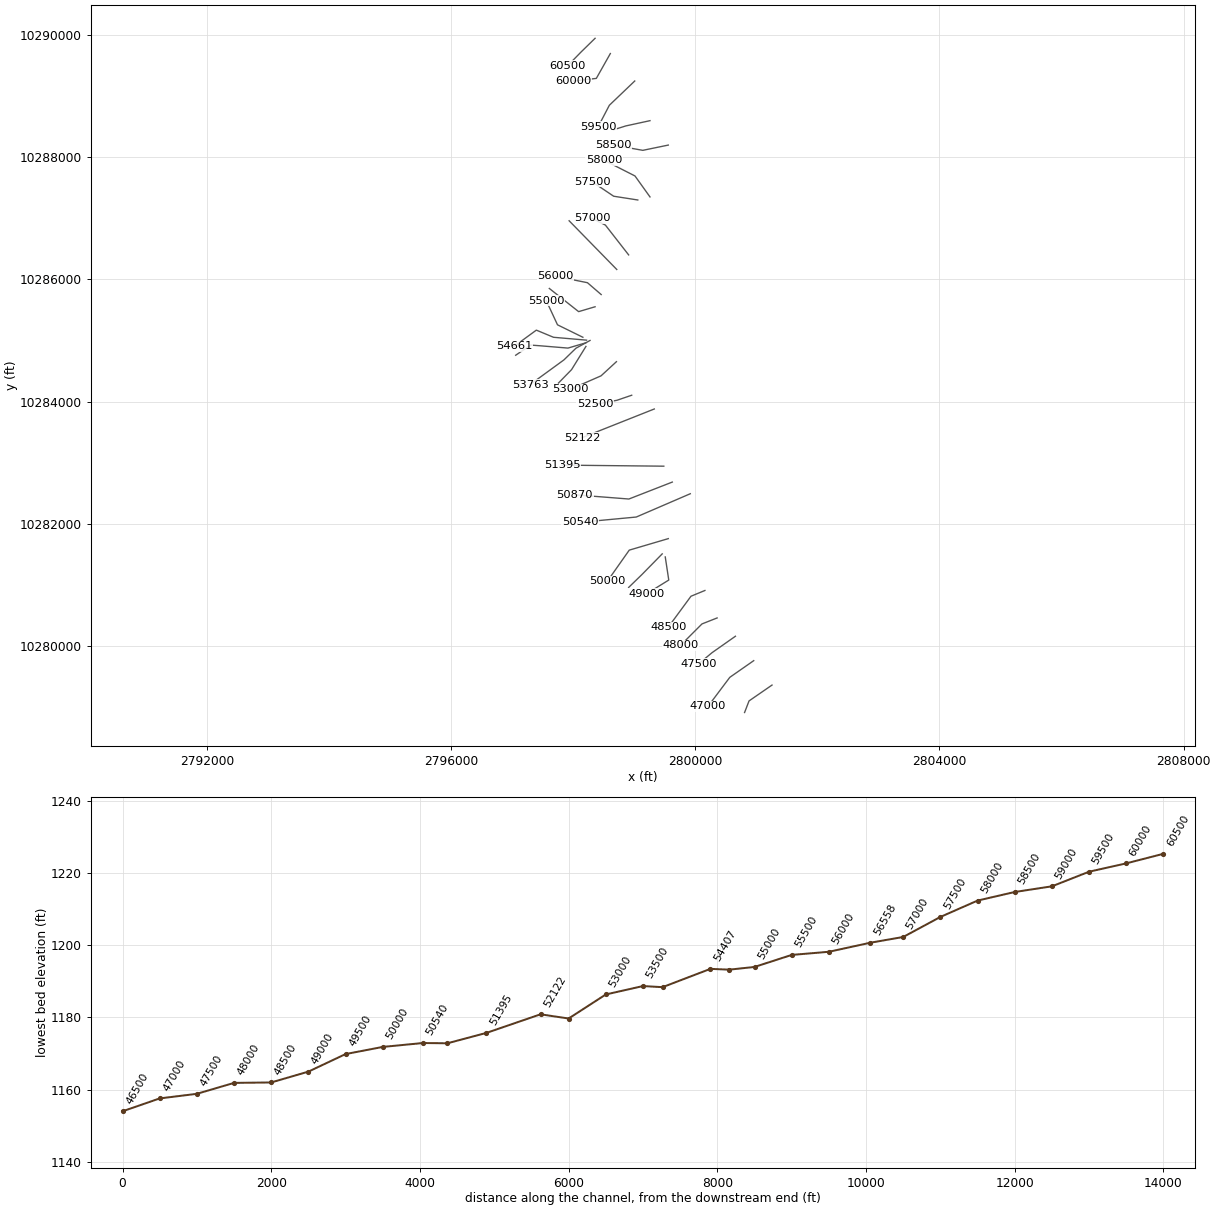
HEC-RAS study PECAN CREEK.prj: PECAN CREEK Base Level Engineering

--- PECAN CREEK.g01 (geometry) --- (continued)

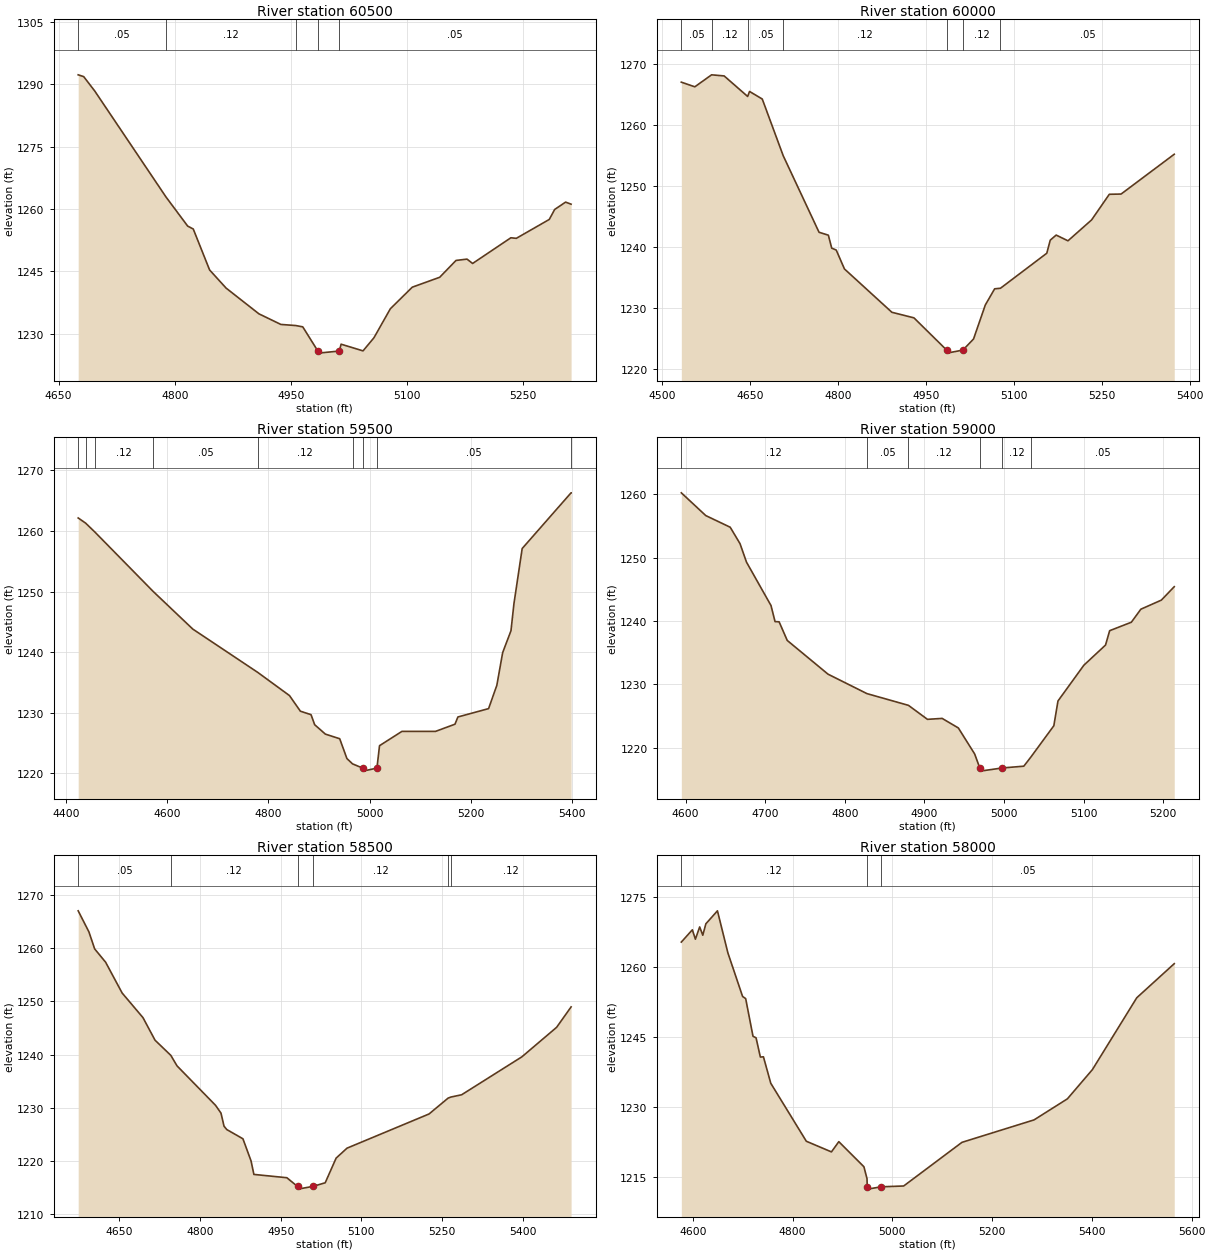
Type RM Length L Ch R = 1 ,60500   ,500,500,500
BEGIN DESCRIPTION:
PECAN CREEK 121.0
END DESCRIPTION:
XS GIS Cut Line= 3
      2798355.71     10289953.14      2798123.46     10289726.08
      2797905.67     10289503.09
#Sta/Elev= 30
  4675.2 1292.25  4682.3 1291.82  4696.5 1288.38  4788.6 1262.87  4816.6 1255.87
  4823.8 1255.17  4844.9 1245.32  4866.2 1240.96  4908.6 1234.77  4936.9 1232.22
  4956.2 1231.95  4965.2 1231.64  4984.7 1225.82  4985.2 1225.32  5012.4 1225.82
  5014.7 1227.47    5043 1225.86  5057.1 1229.01  5078.3 1235.99  5106.6 1241.18
    5142 1243.56  5163.1 1247.61  5177.3 1247.93  5184.5 1246.88  5233.9 1253.06
    5241 1252.93  5283.5 1257.47  5290.5 1259.87  5304.6 1261.64  5311.7 1261.14
#Mann= 5 ,-1 , 0
  4675.2     .05       0  4788.6     .12       0  4956.2     .05       0
  4984.7     .05       0  5012.4     .05       0
Bank Sta=4984.7,5012.4
XS Rating Curve= 0 ,0
Exp/Cntr=0.3,0.1

Type RM Length L Ch R = 1 ,60000   ,500,500,500
BEGIN DESCRIPTION:
PECAN CREEK 120.0
END DESCRIPTION:
XS GIS Cut Line= 3
       2798605.7     10289703.15      2798376.04     10289295.83
      2798005.69     10289253.11
#Sta/Elev= 30
  4532.4 1266.99  4555.4 1266.23    4584 1268.19  4605.4 1268.01  4645.5 1264.65
  4648.7 1265.47  4670.4 1264.23  4706.1 1254.96  4767.2 1242.44  4783.1 1241.96
  4788.8 1239.84  4796.5 1239.53  4810.5 1236.44  4891.4 1229.35    4929 1228.44
  4984.8 1223.17  4985.3 1222.67  5012.5 1223.17  5030.6 1224.98  5050.7 1230.55
  5066.6 1233.19  5076.5 1233.28  5155.5 1239.01  5161.4 1241.15  5171.5 1241.98
  5191.6 1241.04  5231.9 1244.46  5262.1 1248.65  5282.2 1248.69  5372.8  1255.2
#Mann= 7 ,-1 , 0
  4532.4     .05       0    4584     .12       0  4645.5     .05       0
  4706.1     .12       0  4984.8     .07       0  5012.5     .12       0
  5076.5     .05       0
Bank Sta=4984.8,5012.5
XS Rating Curve= 0 ,0
Exp/Cntr=0.3,0.1

Type RM Length L Ch R = 1 ,59500   ,500,500,500
BEGIN DESCRIPTION:
PECAN CREEK 119.0
END DESCRIPTION:
XS GIS Cut Line= 3
      2799005.71     10289253.14      2798589.43     10288855.47
      2798405.68      10288503.1
#Sta/Elev= 30
  4424.3 1262.16  4439.1  1261.3  4457.3 1259.83  4572.3 1250.03  4650.6 1243.81
  4779.3 1236.63  4841.5 1232.83  4862.9 1230.26    4884 1229.68  4891.2 1228.02
  4912.3 1226.47  4940.6 1225.71  4954.8 1222.44  4965.9 1221.56  4985.9 1220.86
  4986.4 1220.36  5014.1 1220.86  5019.2 1224.56  5063.4 1226.92  5129.7 1226.92
  5168.2 1228.11  5173.9  1229.3  5234.5 1230.68  5250.8 1234.53  5262.3 1239.93
  5278.7 1243.54  5284.6 1248.03  5300.8 1257.11  5397.3 1266.31  5397.4 1266.31
#Mann= 9 ,-1 , 0
  4424.3     .12       0  4439.1     .05       0  4457.3     .12       0
  4572.3     .05       0  4779.3     .12       0  4965.9     .05       0
  4985.9     .05       0  5014.1     .05       0  5397.3     .12       0
Bank Sta=4985.9,5014.1
XS Rating Curve= 0 ,0
Exp/Cntr=0.3,0.1

Type RM Length L Ch R = 1 ,59000   ,500,500,500
BEGIN DESCRIPTION:
PECAN CREEK 118.0
END DESCRIPTION:
XS GIS Cut Line= 3
      2799255.67     10288603.11      2798859.62     10288517.02
       2798655.7     10288453.12
#Sta/Elev= 30
  4594.7 1260.22  4625.4 1256.63  4656.1 1254.79  4668.4  1252.2  4676.6 1249.27
  4707.3 1242.44  4712.4  1239.9  4717.5 1239.87  4727.7 1236.93  4778.9 1231.61
  4827.8 1228.54  4879.9 1226.69  4903.8 1224.48  4922.2 1224.63  4942.6 1223.12
  4963.1 1219.01  4969.5 1216.81    4970 1216.31  4997.7 1216.81  5024.8 1217.09
  5033.3 1218.47  5062.5 1223.47  5067.7 1227.38  5100.2 1233.02  5127.4  1236.2
  5132.6 1238.47  5159.8  1239.8  5171.8 1241.86  5197.5 1243.29  5213.7 1245.41
#Mann= 6 ,-1 , 0
  4594.7     .12       0  4827.8     .05       0  4879.9     .12       0
  4969.5     .07       0  4997.7     .12       0  5033.3     .05       0
Bank Sta=4969.5,4997.7
XS Rating Curve= 0 ,0
Exp/Cntr=0.3,0.1

Type RM Length L Ch R = 1 ,58500   ,500,500,500
BEGIN DESCRIPTION:
PECAN CREEK 117.0
END DESCRIPTION:
XS GIS Cut Line= 3
      2799555.66     10288203.11      2799137.88      10288116.8
      2798655.65     10288203.12
#Sta/Elev= 30
  4573.4 1266.97  4593.4 1263.01    4604 1259.83  4624.4 1257.33  4655.1 1251.55
  4693.9 1246.92  4716.3 1242.69  4745.7 1239.84  4757.2 1237.87  4828.7 1230.48
  4838.9 1229.01  4844.6 1226.55  4849.7 1225.92  4879.7 1224.19  4894.8 1220.04
  4900.1  1217.5  4961.4 1216.88  4981.2 1215.24  4981.7 1214.74  5009.5 1215.24
  5032.7 1215.93    5053 1220.56  5073.3 1222.43  5225.7 1228.84  5261.2 1231.82
  5266.4 1232.02  5286.4 1232.45  5398.4 1239.57    5463 1245.11  5489.9 1248.94
#Mann= 6 ,-1 , 0
  4573.4     .05       0  4745.7     .12       0  4981.2     .07       0
  5009.5     .12       0  5261.2     .05       0  5266.4     .12       0
Bank Sta=4981.2,5009.5
XS Rating Curve= 0 ,0
Exp/Cntr=0.3,0.1

Type RM Length L Ch R = 1 ,58000   ,500,500,500
BEGIN DESCRIPTION:
PECAN CREEK 116.0
END DESCRIPTION:
XS GIS Cut Line= 3
      2799255.67     10287353.13       2799009.4     10287697.05
      2798505.65     10287953.13
#Sta/Elev= 30
    4577 1265.31  4599.1 1267.94  4605.2 1265.93  4613.8 1268.56    4620 1266.78
  4626.2 1269.23  4649.4 1272.01  4670.3 1263.01  4699.8 1253.66    4706 1253.19
  4720.7 1245.11  4726.8  1244.8  4735.4 1240.67  4741.6 1240.72  4756.3 1235.05
  4827.6 1222.62  4877.9 1220.34  4892.7 1222.53    4943 1217.16  4949.2 1214.62
  4949.7 1212.86  4950.2 1212.36  4978.1 1212.86  5022.7 1213.03  5139.6 1222.39
  5284.1  1227.2  5350.9 1231.71    5401 1237.97    5490 1253.38  5565.1 1260.68
#Mann= 3 ,-1 , 0
    4577     .12       0  4949.7     .05       0  4978.1     .05       0
Bank Sta=4949.7,4978.1
XS Rating Curve= 0 ,0
Exp/Cntr=0.3,0.1

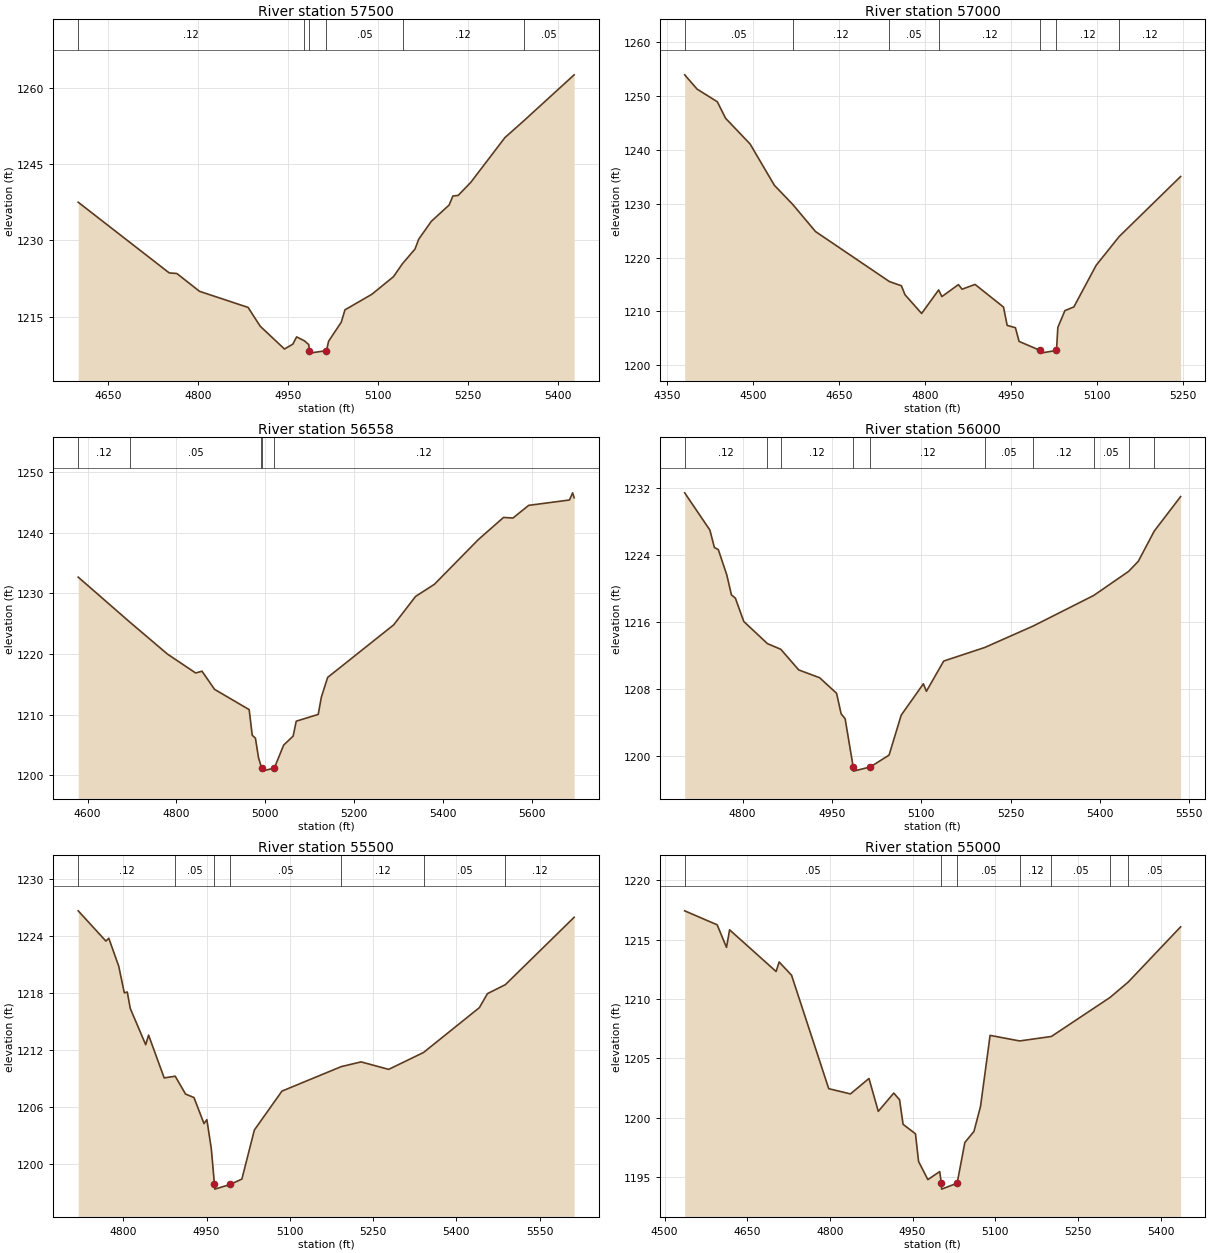
Type RM Length L Ch R = 1 ,57500   ,500,500,500
BEGIN DESCRIPTION:
PECAN CREEK 115.0
END DESCRIPTION:
XS GIS Cut Line= 3
      2799055.69     10287303.11      2798660.27     10287364.78
      2798305.72     10287603.09
#Sta/Elev= 30
  4599.8 1237.47  4751.6 1223.59  4764.4 1223.47  4802.2 1219.97  4883.2 1216.81
  4903.4 1213.12  4943.9 1208.64  4957.9  1209.6  4964.2 1211.02  4977.3 1210.24
  4984.4 1209.51  4985.6 1208.33  4986.1 1207.83    5014 1208.33  5017.6 1210.18
  5038.7 1213.91  5044.8 1216.33  5089.7 1219.39  5125.7 1222.84  5140.9 1225.42
  5161.7 1228.28  5167.8 1230.19  5188.8 1233.71  5218.7 1236.93  5224.8 1238.69
  5233.7 1238.81  5254.7 1241.37  5311.7 1250.17  5343.6 1253.51  5427.2  1262.5
#Mann= 6 ,-1 , 0
  4599.8     .12       0  4977.3     .05       0  4985.6     .05       0
    5014     .05       0  5140.9     .12       0  5343.6     .05       0
Bank Sta=4985.6,5014
XS Rating Curve= 0 ,0
Exp/Cntr=0.3,0.1

Type RM Length L Ch R = 1 ,57000   ,442,442,442
BEGIN DESCRIPTION:
PECAN CREEK 114.0
END DESCRIPTION:
XS GIS Cut Line= 3
      2798905.67     10286403.13      2798524.62     10286891.83
      2798305.68     10287003.11
#Sta/Elev= 30
  4380.3 1253.88    4402 1251.23  4437.3 1248.88  4451.7 1245.82  4494.4 1241.06
  4536.8  1233.4  4569.1 1229.82  4608.5 1224.83  4737.5 1215.55  4758.4 1214.77
  4764.7 1213.11  4793.7 1209.63  4823.4 1213.99    4829 1212.76  4857.9 1214.98
  4864.3 1214.13  4886.9 1215.02  4936.6 1210.82    4943 1207.42  4957.4 1206.99
  4963.8 1204.45  5000.5 1202.78    5001 1202.28    5029 1202.78  5031.4 1207.05
  5043.7 1210.16  5059.3 1210.84  5098.2 1218.56  5138.5 1223.91  5245.6 1235.03
#Mann= 7 ,-1 , 0
  4380.3     .05       0  4569.1     .12       0  4737.5     .05       0
  4823.4     .12       0  5000.5     .07       0    5029     .12       0
  5138.5     .12       0
Bank Sta=5000.5,5029
XS Rating Curve= 0 ,0
Exp/Cntr=0.3,0.1

Type RM Length L Ch R = 1 ,56558   ,558,558,558
BEGIN DESCRIPTION:
Mapping XS 871d2a23
END DESCRIPTION:
XS GIS Cut Line= 2
      2798711.04     10286164.26      2797930.21     10286962.45
#Sta/Elev= 30
    4579  1232.7  4695.8 1225.24    4780    1220  4843.5 1216.88  4857.7 1217.18
    4886 1214.18  4963.9 1210.84  4970.8 1206.61    4978 1206.13    4985 1202.89
  4991.4 1201.34    4992 1201.19  4992.5 1200.69  5020.5 1201.19  5041.6 1204.99
  5062.9 1206.47  5069.9 1208.93  5119.4 1210.05  5126.4 1212.89  5140.6 1216.15
  5289.2 1224.82  5338.6 1229.52    5381 1231.52  5480.1 1238.91  5536.6 1242.55
  5557.8 1242.45  5593.2 1244.54  5685.1 1245.43  5692.2 1246.61  5695.6  1245.8
#Mann= 5 ,-1 , 0
    4579     .12       0  4695.8     .05       0  4991.4     .12       0
    4992     .07       0  5020.5     .12       0
Bank Sta=4992,5020.5
XS Rating Curve= 0 ,0
Exp/Cntr=0.3,0.1

Type RM Length L Ch R = 1 ,56000   ,500,500,500
BEGIN DESCRIPTION:
PECAN CREEK 112.0
END DESCRIPTION:
XS GIS Cut Line= 3
      2798455.71     10285753.09      2798230.56      10285947.4
       2797705.7     10286053.11
#Sta/Elev= 30
  4702.6  1231.4  4744.9 1226.96  4752.5 1224.88  4759.1 1224.62  4773.4 1221.58
  4781.1 1219.22  4787.7 1218.83  4801.9 1216.04  4841.6  1213.4  4864.1 1212.72
  4894.1 1210.26  4929.2 1209.33  4957.7 1207.47  4965.3 1205.02    4972 1204.44
  4985.6 1198.68  4986.1 1198.18  5014.3 1198.68  5045.8 1200.09  5066.2 1204.86
  5103.4  1208.6  5108.5 1207.71  5137.6 1211.32  5206.5 1212.94  5287.8  1215.5
  5389.5 1219.15    5448 1222.02  5464.3 1223.22  5491.1 1226.83  5535.4 1230.95
#Mann= 10 ,-1 , 0
  4702.6     .12       0  4841.6     .05       0  4864.1     .12       0
  4985.6     .07       0  5014.3     .12       0  5206.5     .05       0
  5287.8     .12       0  5389.5     .05       0    5448     .12       0
  5491.1     .05       0
Bank Sta=4985.6,5014.3
XS Rating Curve= 0 ,0
Exp/Cntr=0.3,0.1

Type RM Length L Ch R = 1 ,55500   ,500,500,500
BEGIN DESCRIPTION:
PECAN CREEK 111.0
END DESCRIPTION:
XS GIS Cut Line= 3
      2798355.67     10285553.11      2798085.93     10285473.29
      2797605.68     10285853.12
#Sta/Elev= 30
  4718.7 1226.64  4768.6 1223.45  4773.8 1223.75  4791.7 1220.81  4801.8 1217.99
  4807.1 1218.09  4812.5 1216.35  4840.3 1212.53  4845.5 1213.54  4873.6 1209.03
  4893.5 1209.21  4912.1 1207.33  4927.3 1206.96  4945.3 1204.22  4950.5 1204.63
  4958.5 1201.58  4964.2 1197.81  4964.7 1197.31  4992.9 1197.81  5013.6 1198.37
  5036.1 1203.54  5085.8 1207.64  5192.6 1210.22  5228.4 1210.72  5278.1 1209.93
  5340.9 1211.71  5441.6 1216.44    5456 1217.91  5488.4 1218.86  5612.3 1225.96
#Mann= 7 ,-1 , 0
  4718.7     .12       0  4893.5     .05       0  4964.2     .05       0
  4992.9     .05       0  5192.6     .12       0  5340.9     .05       0
  5488.4     .12       0
Bank Sta=4964.2,4992.9
XS Rating Curve= 0 ,0
Exp/Cntr=0.3,0.1

Type RM Length L Ch R = 1 ,55000   ,339,339,339
BEGIN DESCRIPTION:
PECAN CREEK 110.0
END DESCRIPTION:
XS GIS Cut Line= 3
      2798155.67     10285053.12      2797739.68      10285257.3
      2797555.68     10285653.12
#Sta/Elev= 30
  4536.6 1217.42  4595.6 1216.24  4612.5 1214.34  4618.1 1215.82  4702.5 1212.31
    4708 1213.11  4730.5    1212    4798 1202.44  4837.4    1202    4871  1203.3
  4887.9 1200.53    4916 1202.07  4926.5 1201.51  4932.9 1199.44  4955.4 1198.64
    4961 1196.31  4977.9 1194.78  4999.4 1195.46  5002.3 1194.48  5002.8 1193.98
    5031 1194.48    5045 1197.91  5061.5 1198.84  5073.4 1200.94  5090.8 1206.93
  5144.5 1206.46  5202.1 1206.84  5308.3 1210.12  5341.2 1211.41  5436.5 1216.07
#Mann= 7 ,-1 , 0
  4536.6     .05       0  5002.3     .03       0    5031     .05       0
  5144.5     .12       0  5202.1     .05       0  5308.3     .12       0
  5341.2     .05       0
Bank Sta=5002.3,5031
XS Rating Curve= 0 ,0
Exp/Cntr=0.3,0.1

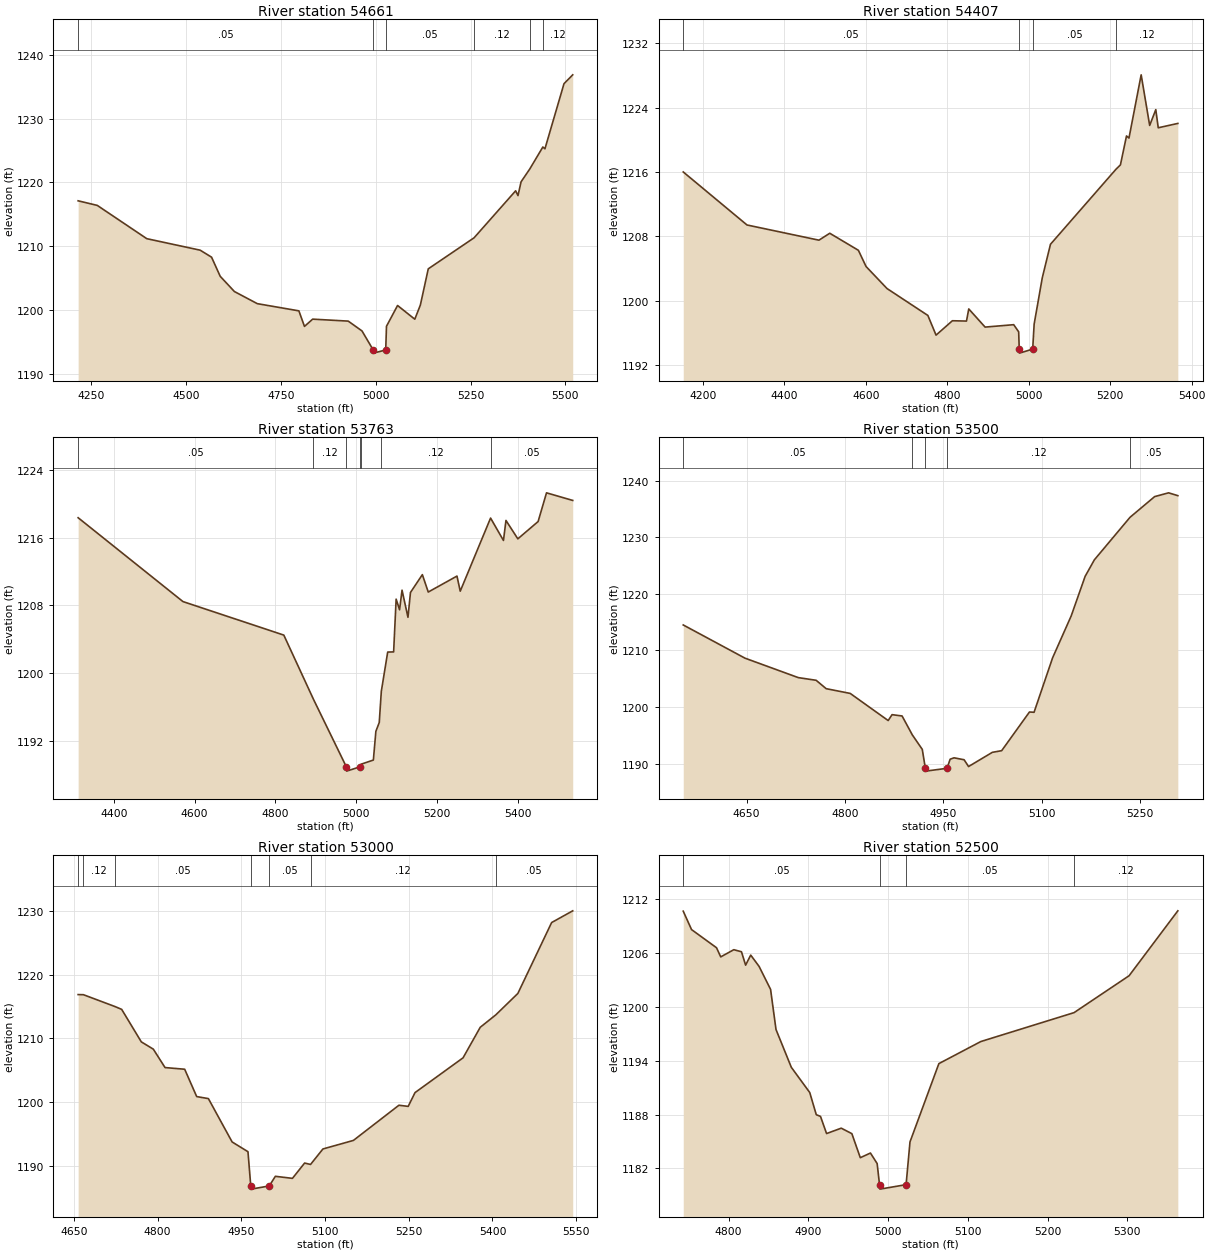
Type RM Length L Ch R = 1 ,54661   ,254,254,254
BEGIN DESCRIPTION:
Mapping XS 00442dab
END DESCRIPTION:
XS GIS Cut Line= 4
      2798215.88     10285006.04       2797674.2     10285052.92
      2797392.95     10285170.11      2797025.78     10284901.89
#Sta/Elev= 30
  4216.2 1217.12  4266.6  1216.4  4397.1 1211.18  4537.6 1209.38  4567.7 1208.28
  4590.5 1205.28  4627.9 1202.89  4688.2 1200.99  4797.8 1199.86  4812.5 1197.42
  4834.1 1198.56  4927.8 1198.25  4964.1 1196.71  4993.6 1193.73  4994.2 1193.23
  5026.6 1193.73  5028.6 1197.44  5057.8  1200.7  5103.2 1198.55  5117.9 1200.78
  5138.7 1206.45  5259.4 1211.32  5368.9 1218.69  5375.1 1217.94  5383.2  1220.1
  5406.1 1222.11  5440.6 1225.56  5446.1 1225.28  5496.3 1235.49  5519.3 1236.88
#Mann= 6 ,-1 , 0
  4216.2     .05       0  4993.6     .03       0  5026.6     .05       0
  5259.4     .12       0  5406.1     .05       0  5440.6     .12       0
Bank Sta=4993.6,5026.6
XS Rating Curve= 0 ,0
Exp/Cntr=0.3,0.1

Type RM Length L Ch R = 1 ,54407   ,644,644,644
BEGIN DESCRIPTION:
Mapping XS 310aa956
END DESCRIPTION:
XS GIS Cut Line= 5
       2798202.8     10284961.76      2797911.18     10284875.84
      2797439.82      10284914.9       2797299.2     10284925.31
      2797054.44     10284758.67
#Sta/Elev= 30
    4152    1216  4308.5  1209.4  4485.1 1207.51  4511.7 1208.37  4581.9 1206.25
  4600.8 1204.23  4652.2 1201.49  4752.5 1198.14  4772.6 1195.69  4812.7 1197.48
  4847.3 1197.44  4852.9 1198.95    4893 1196.69  4963.2 1196.99  4975.4  1196.1
  4976.8 1193.95  4977.4 1193.45  5009.8 1193.95  5013.4 1197.07  5033.4 1202.84
  5053.5    1207  5214.5 1216.35  5225.2 1216.88  5240.1 1220.48  5246.2 1220.22
  5276.1 1228.09    5297 1221.79    5312 1223.76    5318  1221.5  5366.1 1222.04
#Mann= 4 ,-1 , 0
    4152     .05       0  4976.8     .03       0  5009.8     .05       0
  5214.5     .12       0
Bank Sta=4976.8,5009.8
XS Rating Curve= 0 ,0
Exp/Cntr=0.3,0.1

Type RM Length L Ch R = 1 ,53763   ,263,263,263
BEGIN DESCRIPTION:
Mapping XS 49661373
END DESCRIPTION:
XS GIS Cut Line= 4
      2798273.13     10285000.82      2798041.39     10284873.23
      2797846.07     10284683.13       2797290.6      10284278.2
#Sta/Elev= 30
  4311.6 1218.39  4571.1 1208.46  4820.8 1204.49  4894.2 1196.89  4975.7 1188.88
  4976.3 1188.38  5008.8 1188.88  5012.7 1189.21  5042.5 1189.69  5048.7 1193.09
  5057.1 1194.14  5062.2 1197.83    5078 1202.48  5092.7  1202.5  5098.9 1208.75
  5107.4 1207.49  5113.5 1209.81  5128.2  1206.6  5134.4 1209.54  5163.8 1211.65
  5178.4 1209.59  5249.5 1211.48  5257.6 1209.69  5332.7 1218.35  5364.6  1215.7
  5370.8 1218.07  5400.2 1215.89  5450.4 1217.94  5471.2 1221.34  5536.1 1220.44
#Mann= 7 ,-1 , 0
  4311.6     .05       0  4894.2     .12       0  4975.7     .07       0
  5008.8     .12       0  5012.7     .05       0  5062.2     .12       0
  5332.7     .05       0
Bank Sta=4975.7,5008.8
XS Rating Curve= 0 ,0
Exp/Cntr=0.3,0.1

Type RM Length L Ch R = 1 ,53500   ,500,500,500
BEGIN DESCRIPTION:
PECAN CREEK 107.0
END DESCRIPTION:
XS GIS Cut Line= 3
      2798205.69     10284903.13      2797970.53     10284523.34
      2797755.66     10284303.09
#Sta/Elev= 30
  4553.3  1214.5  4647.4 1208.64  4728.8  1205.2    4756 1204.73  4771.3 1203.25
    4808 1202.41  4865.9 1197.62  4871.8 1198.66  4887.1 1198.43  4902.6 1195.11
  4917.9 1192.53  4922.6 1189.19  4923.2 1188.69  4955.7 1189.19  4960.4 1190.79
  4966.3 1191.04  4981.7  1190.7  4988.5  1189.5  5024.8 1192.01    5039  1192.3
  5081.4 1199.13  5088.4 1199.08  5116.7  1208.7    5145 1216.08  5166.3 1223.08
  5180.4    1226  5234.8 1233.51  5272.3 1237.16  5293.6 1237.83  5307.7 1237.33
#Mann= 5 ,-1 , 0
  4553.3     .05       0  4902.6     .12       0  4922.6     .07       0
  4955.7     .12       0  5234.8     .05       0
Bank Sta=4922.6,4955.7
XS Rating Curve= 0 ,0
Exp/Cntr=0.3,0.1

Type RM Length L Ch R = 1 ,53000   ,500,500,500
BEGIN DESCRIPTION:
PECAN CREEK 106.0
END DESCRIPTION:
XS GIS Cut Line= 3
      2798705.71     10284653.13       2798453.8     10284421.22
      2797955.66      10284203.1
#Sta/Elev= 30
  4657.6 1216.88  4667.1 1216.86  4723.7    1215  4735.6 1214.56  4770.8 1209.46
  4792.3 1208.32  4813.3 1205.43  4848.5 1205.17    4870 1200.88    4891 1200.56
  4933.5 1193.76  4961.9 1192.23  4966.9 1186.86  4967.5 1186.36    5000 1186.86
    5011 1188.37  5041.6 1188.05  5063.4 1190.45    5074 1190.23  5096.2 1192.66
  5150.8    1194  5232.4 1199.52    5249 1199.34  5261.2  1201.5  5347.3 1206.96
  5378.1 1211.75  5406.1 1213.71  5445.5 1217.06    5506 1228.18  5543.8 1230.02
#Mann= 7 ,-1 , 0
  4657.6     .05       0  4667.1     .12       0  4723.7     .05       0
  4966.9     .05       0    5000     .05       0    5074     .12       0
  5406.1     .05       0
Bank Sta=4966.9,5000
XS Rating Curve= 0 ,0
Exp/Cntr=0.3,0.1

Type RM Length L Ch R = 1 ,52500   ,378,378,378
BEGIN DESCRIPTION:
PECAN CREEK 105.0
END DESCRIPTION:
XS GIS Cut Line= 3
       2798955.7     10284103.12      2798712.75     10284019.92
      2798355.65      10283953.1
#Sta/Elev= 30
  4743.2 1210.66  4753.6 1208.61  4784.9 1206.59  4790.2 1205.57  4806.6 1206.37
  4816.2 1206.14  4821.4 1204.65  4827.8 1205.77  4838.3 1204.51  4852.7 1201.95
  4859.5 1197.48  4878.7 1193.27  4901.8 1190.46    4910 1187.99  4915.3  1187.8
  4922.9 1185.89  4941.3 1186.49  4954.6 1185.88  4965.2  1183.2  4977.9 1183.72
  4986.3 1182.55  4989.3  1180.2  4989.9  1179.7  5022.6  1180.2  5027.5 1184.96
  5063.7 1193.68  5116.3 1196.14  5233.2 1199.36  5302.2 1203.47  5363.3  1210.7
#Mann= 4 ,-1 , 0
  4743.2     .05       0  4989.3     .05       0  5022.6     .05       0
  5233.2     .12       0
Bank Sta=4989.3,5022.6
XS Rating Curve= 0 ,0
Exp/Cntr=0.3,0.1

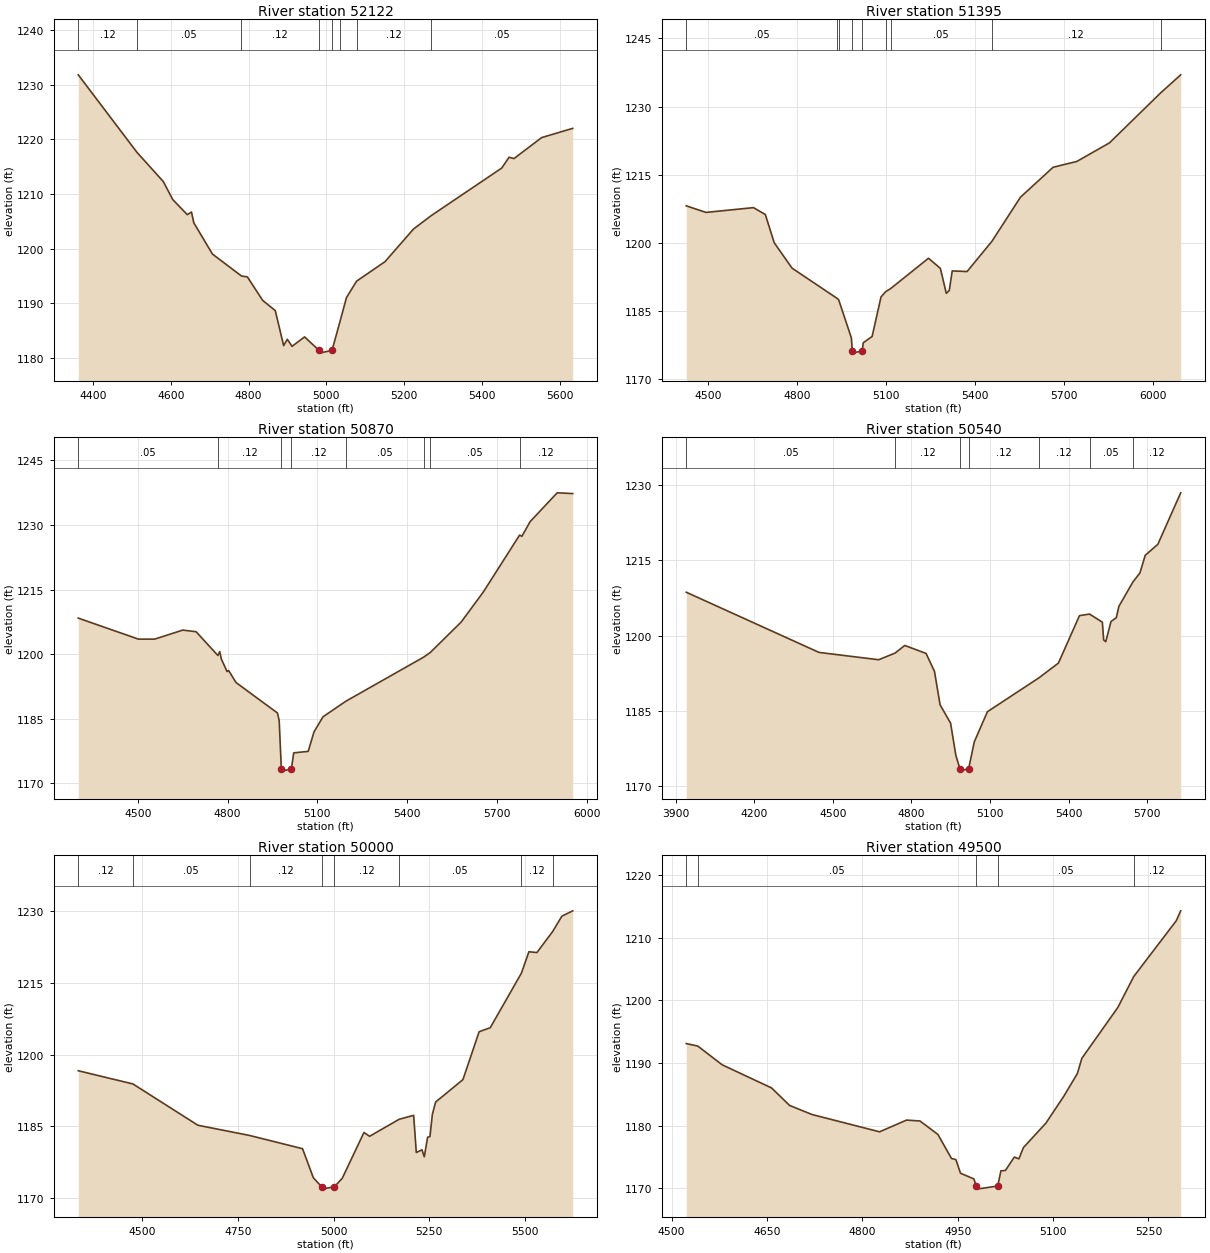
Type RM Length L Ch R = 1 ,52122   ,727,727,727
BEGIN DESCRIPTION:
Mapping XS a8a1c17a
END DESCRIPTION:
XS GIS Cut Line= 2
      2799326.04     10283877.84      2798145.49     10283409.09
#Sta/Elev= 30
  4362.5 1231.81  4513.2 1217.63    4581 1212.27  4605.3 1208.97  4642.6 1206.21
  4653.4 1206.69  4659.3 1204.72  4707.2    1199  4781.8 1194.98    4797 1194.81
  4836.3 1190.51  4868.6 1188.65  4890.1 1182.23  4899.6  1183.4  4911.6  1182.1
  4943.9 1183.83    4981 1181.36  4981.6 1180.86  5014.4 1181.36  5034.7  1186.6
  5051.5 1191.03  5077.6 1194.04  5150.6 1197.61  5223.6 1203.57  5268.9 1206.02
  5450.3 1214.74  5469.2 1216.72  5481.9 1216.48  5552.9 1220.32  5632.7 1222.01
#Mann= 8 ,-1 , 0
  4362.5     .12       0  4513.2     .05       0  4781.8     .12       0
    4981     .07       0  5014.4     .12       0  5034.7     .05       0
  5077.6     .12       0  5268.9     .05       0
Bank Sta=4981,5014.4
XS Rating Curve= 0 ,0
Exp/Cntr=0.3,0.1

Type RM Length L Ch R = 1 ,51395   ,525,525,525
BEGIN DESCRIPTION:
Mapping XS 8ee69f89
END DESCRIPTION:
XS GIS Cut Line= 2
      2799482.24     10282940.33      2797815.63     10282957.69
#Sta/Elev= 30
  4426.7 1208.15  4493.3  1206.7  4653.3 1207.75  4693.3 1206.24  4723.3 1200.02
  4783.3 1194.43  4934.5 1187.81  4940.5 1187.47  4983.3 1179.08  4986.6 1176.22
  4987.2 1175.72    5020 1176.22  5023.3    1178  5053.3 1179.39  5083.3  1188.1
    5099 1189.25  5115.9 1189.94  5243.3 1196.61  5283.3 1194.38  5303.3 1188.89
  5313.3 1189.51  5323.3 1193.82  5373.3 1193.68    5457 1200.33  5553.3 1210.05
  5663.3 1216.64  5743.3 1217.92  5853.3 1222.01  6026.1 1233.03  6093.4 1236.99
#Mann= 9 ,-1 , 0
  4426.7     .05       0  4934.5     .12       0  4940.5     .05       0
  4986.6     .05       0    5020     .05       0    5099     .12       0
  5115.9     .05       0    5457     .12       0  6026.1     .05       0
Bank Sta=4986.6,5020
XS Rating Curve= 0 ,0
Exp/Cntr=0.3,0.1

Type RM Length L Ch R = 1 ,50870   ,330,330,330
BEGIN DESCRIPTION:
Mapping XS fe28b703
END DESCRIPTION:
XS GIS Cut Line= 3
      2799621.13     10282679.91      2798909.36     10282402.14
      2798023.93     10282471.58
#Sta/Elev= 30
  4301.1 1208.37  4502.1 1203.49  4556.4 1203.49  4650.5 1205.59  4694.9 1205.21
  4767.7 1199.69  4773.8 1200.61  4779.3 1198.87  4798.3 1195.96  4803.6  1196.2
  4828.1 1193.42  4966.7 1186.34  4972.5 1184.57  4979.7 1173.34  4980.4 1172.84
  5013.3 1173.34    5021 1177.08  5069.5 1177.43  5088.9 1181.97    5119 1185.46
  5195.7 1189.09    5456 1199.34  5477.5  1200.4  5580.4 1207.44  5654.4 1214.41
  5775.8 1227.64  5783.5 1227.37  5811.1 1230.78  5901.4 1237.46  5953.3 1237.29
#Mann= 8 ,-1 , 0
  4301.1     .05       0  4767.7     .12       0  4979.7     .07       0
  5013.3     .12       0  5195.7     .05       0    5456     .12       0
  5477.5     .05       0  5775.8     .12       0
Bank Sta=4979.7,5013.3
XS Rating Curve= 0 ,0
Exp/Cntr=0.3,0.1

Type RM Length L Ch R = 1 ,50540   ,540,540,540
BEGIN DESCRIPTION:
Mapping XS 8dc4426a
END DESCRIPTION:
XS GIS Cut Line= 3
      2799916.31     10282488.95      2799030.88       10282107.
      2798110.77      10282020.2
#Sta/Elev= 30
    3940 1208.66  4447.1 1196.63    4675 1195.17  4737.3 1196.49  4774.5 1198.02
    4856 1196.43  4888.2 1192.83  4909.5 1186.17  4949.7 1182.49  4969.8 1176.05
  4985.1 1173.41  4985.8 1172.91  5018.7 1173.41  5040.1 1178.75  5090.3 1184.78
  5287.3 1191.56  5361.5  1194.5  5441.9 1203.98  5480.4 1204.29  5529.3 1202.68
  5534.3 1199.11  5542.3 1198.78  5562.4 1202.82  5582.5 1203.56  5592.5 1205.84
  5646.2 1210.72  5672.9 1212.52    5693 1216.03  5741.2 1218.23  5828.5 1228.52
#Mann= 7 ,-1 , 0
    3940     .05       0  4737.3     .12       0  4985.1     .05       0
  5018.7     .12       0  5287.3     .12       0  5480.4     .05       0
  5646.2     .12       0
Bank Sta=4985.1,5018.7
XS Rating Curve= 0 ,0
Exp/Cntr=0.3,0.1

Type RM Length L Ch R = 1 ,50000   ,500,500,500
BEGIN DESCRIPTION:
PECAN CREEK 100.0
END DESCRIPTION:
XS GIS Cut Line= 3
      2799555.71     10281753.12      2798915.64     10281564.44
       2798555.7     10281053.13
#Sta/Elev= 30
  4332.7 1196.63  4475.7 1193.86  4645.5 1185.21  4780.7 1183.07    4919  1180.3
  4947.1 1174.24  4968.8 1172.33  4969.5 1171.83  5002.5 1172.33    5023 1174.13
  5079.6  1183.7  5094.4  1182.9  5171.3 1186.45  5209.5 1187.29  5216.4  1179.5
  5231.2 1180.07  5237.3 1178.61    5246  1182.7  5252.1 1182.84  5258.4 1187.51
  5266.9 1190.07  5338.3 1194.77  5380.7 1204.81  5409.7 1205.64  5491.2 1217.08
  5510.8 1221.56  5531.7 1221.39  5573.1 1225.82    5597 1229.01  5625.3 1230.13
#Mann= 8 ,-1 , 0
  4332.7     .12       0  4475.7     .05       0  4780.7     .12       0
  4968.8     .07       0  5002.5     .12       0  5171.3     .05       0
  5491.2     .12       0  5573.1     .05       0
Bank Sta=4968.8,5002.5
XS Rating Curve= 0 ,0
Exp/Cntr=0.3,0.1

Type RM Length L Ch R = 1 ,49500   ,500,500,500
BEGIN DESCRIPTION:
PECAN CREEK 99.0
END DESCRIPTION:
XS GIS Cut Line= 3
      2799455.67     10281503.09       2799121.6     10281162.61
      2798905.72     10280953.15
#Sta/Elev= 30
    4523 1193.09  4541.2 1192.69  4579.5  1189.7  4657.3    1186  4685.6 1183.21
  4720.9 1181.76  4827.1    1179  4869.5 1180.87  4890.7 1180.73  4918.9 1178.58
  4940.2 1174.75  4947.2 1174.56  4954.4 1172.39  4975.5 1171.48  4979.3 1170.35
  4979.9 1169.85    5013 1170.35    5018 1172.78    5025 1172.82  5039.1 1174.97
  5046.3 1174.68  5053.3 1176.47  5088.8 1180.39    5117 1184.69  5138.2 1188.29
  5145.3 1190.73  5201.9 1198.85    5227  1203.8  5293.8 1212.69  5300.8 1214.28
#Mann= 5 ,-1 , 0
    4523     .12       0  4541.2     .05       0  4979.3     .05       0
    5013     .05       0    5227     .12       0
Bank Sta=4979.3,5013
XS Rating Curve= 0 ,0
Exp/Cntr=0.3,0.1

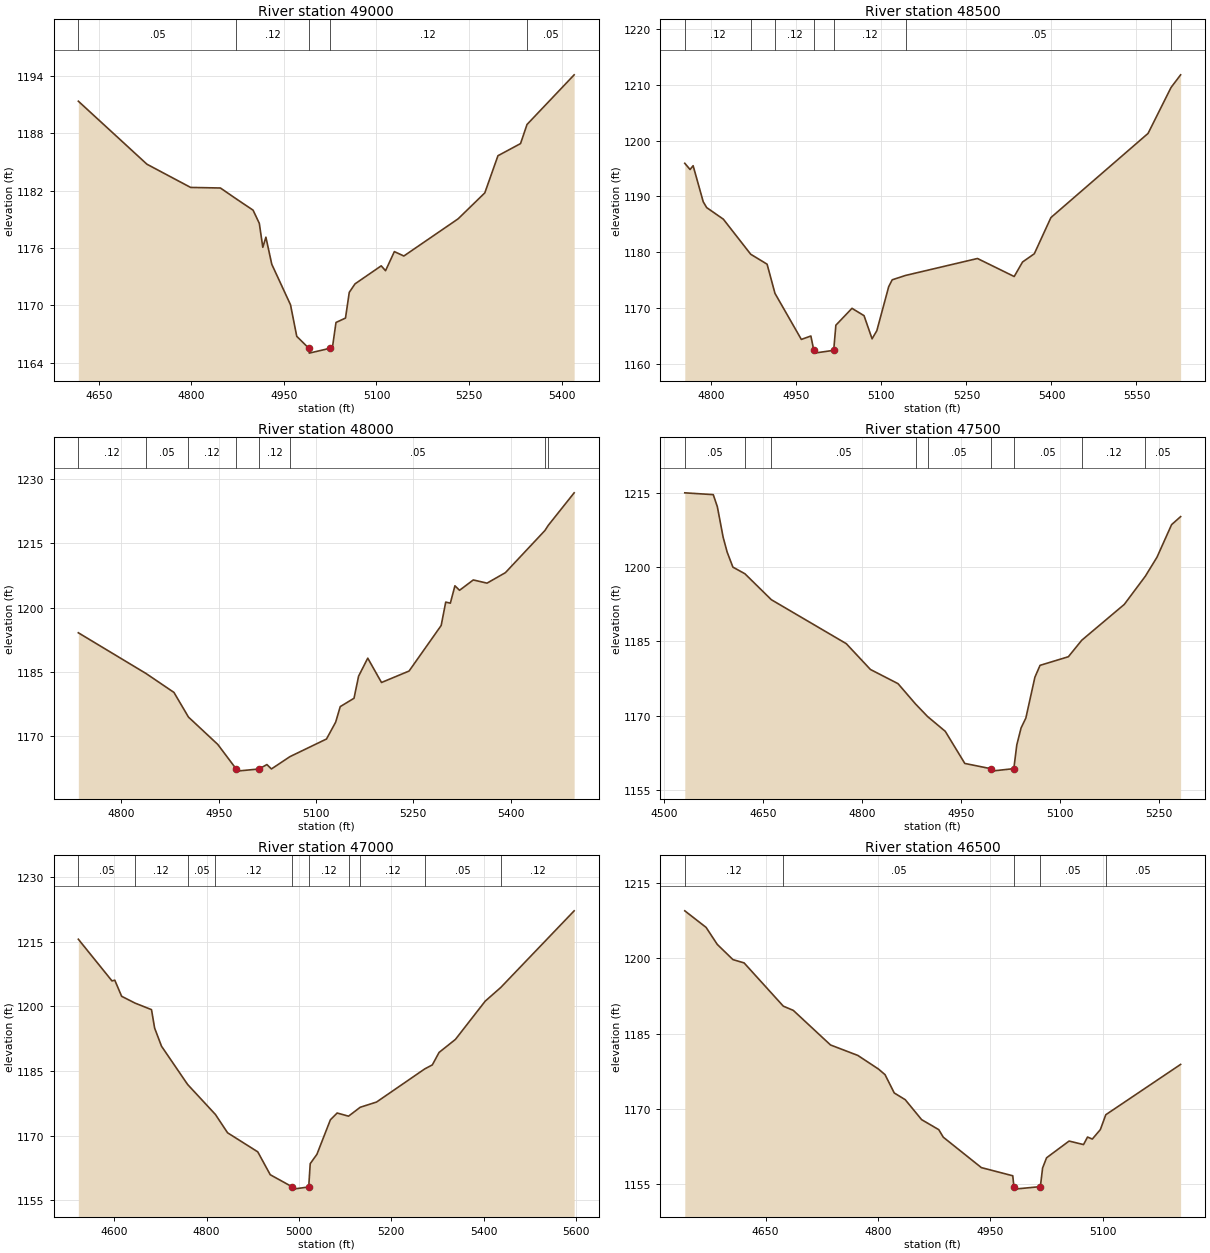
Type RM Length L Ch R = 1 ,49000   ,500,500,500
BEGIN DESCRIPTION:
PECAN CREEK 98.0
END DESCRIPTION:
XS GIS Cut Line= 3
      2799505.69     10281453.06      2799563.24     10281074.21
      2799205.68     10280853.11
#Sta/Elev= 30
  4616.8 1191.37    4728 1184.77  4798.8 1182.34  4847.1 1182.28    4873 1181.13
    4900 1179.96  4910.1 1178.58  4915.8 1176.07  4920.8 1177.13  4930.3  1174.3
  4960.7 1170.05  4970.8 1166.75  4990.5 1165.49  4991.1 1164.99  5024.2 1165.49
  5028.6 1165.57  5034.4  1168.2  5049.8 1168.66  5055.9 1171.35  5065.2 1172.24
  5107.7 1174.13  5114.7 1173.62    5129 1175.62  5144.4 1175.16  5232.3 1179.05
  5275.6 1181.77  5296.9 1185.66  5333.5 1186.93    5344 1188.93  5420.4 1194.13
#Mann= 5 ,-1 , 0
  4616.8     .05       0    4873     .12       0  4990.5     .07       0
  5024.2     .12       0    5344     .05       0
Bank Sta=4990.5,5024.2
XS Rating Curve= 0 ,0
Exp/Cntr=0.3,0.1

Type RM Length L Ch R = 1 ,48500   ,500,500,500
BEGIN DESCRIPTION:
PECAN CREEK 97.0
END DESCRIPTION:
XS GIS Cut Line= 3
      2800155.73     10280903.13      2799927.58       10280809.
      2799555.67     10280303.09
#Sta/Elev= 30
  4753.2 1195.93  4762.5 1194.82  4767.9  1195.5  4785.7 1189.06  4791.8 1188.01
  4821.2 1185.94  4869.5 1179.67  4898.4 1177.89  4912.3 1172.67  4958.8 1164.44
  4975.6 1165.05  4980.8 1162.49  4981.5 1161.99  5015.9 1162.49  5019.7 1166.98
  5048.1    1170  5069.4 1168.69  5083.6 1164.55    5092 1166.01  5112.9 1173.87
  5119.1  1175.1  5142.6 1175.88  5269.5 1178.91  5334.3 1175.69    5349 1178.28
  5369.8 1179.76  5399.1 1186.23  5570.4 1201.27  5611.1  1209.5  5627.9 1211.75
#Mann= 7 ,-1 , 0
  4753.2     .12       0  4869.5     .05       0  4912.3     .12       0
  4980.8     .07       0  5015.9     .12       0  5142.6     .05       0
  5611.1     .12       0
Bank Sta=4980.8,5015.9
XS Rating Curve= 0 ,0
Exp/Cntr=0.3,0.1

Type RM Length L Ch R = 1 ,48000   ,500,500,500
BEGIN DESCRIPTION:
PECAN CREEK 96.0
END DESCRIPTION:
XS GIS Cut Line= 3
      2800355.66      10280453.1      2800107.88     10280355.23
       2799755.7     10280003.13
#Sta/Elev= 30
  4733.6 1194.12  4837.8 1184.64    4881 1180.22  4903.4 1174.47  4948.6 1168.09
    4977 1162.37  4977.8 1161.87  5012.1 1162.37  5024.3  1163.4  5031.3 1162.38
    5060 1165.26  5116.2 1169.36  5130.3 1173.28  5137.4 1176.91  5158.6 1178.85
  5165.7 1184.01  5179.8  1188.2    5201 1182.53  5243.5  1185.2    5293 1195.82
    5300 1201.27  5307.1 1201.02  5314.2 1205.07  5321.3 1204.02  5342.5 1206.43
  5363.7 1205.69    5392 1208.13  5452.9 1217.95  5458.1 1219.16    5498 1226.74
#Mann= 8 ,-1 , 0
  4733.6     .12       0  4837.8     .05       0  4903.4     .12       0
    4977     .07       0  5012.1     .12       0    5060     .05       0
  5452.9     .12       0  5458.1     .05       0
Bank Sta=4977,5012.1
XS Rating Curve= 0 ,0
Exp/Cntr=0.3,0.1

Type RM Length L Ch R = 1 ,47500   ,500,500,500
BEGIN DESCRIPTION:
PECAN CREEK 95.0
END DESCRIPTION:
XS GIS Cut Line= 3
       2800655.7     10280153.12      2800272.46      10279883.8
      2800055.69     10279703.12
#Sta/Elev= 30
  4531.6 1214.96  4574.7 1214.59  4580.9 1212.15  4589.6 1206.03  4595.7 1203.02
  4604.4 1199.98  4622.6 1198.64  4662.6 1193.41  4776.1 1184.54  4812.6 1179.34
  4854.4 1176.48  4880.9 1172.38  4899.2 1169.84  4925.9 1166.87  4955.5 1160.39
  4994.5 1159.34  4995.3 1158.84  5029.7 1159.34  5034.2 1164.13  5040.7 1167.56
  5047.9 1169.54  5061.6 1177.78  5069.4 1180.17  5112.3 1181.91  5132.5 1185.23
  5196.9 1192.46  5228.7 1198.13  5246.4 1201.97  5268.5 1208.54  5282.2 1210.16
#Mann= 9 ,-1 , 0
  4531.6     .05       0  4622.6     .12       0  4662.6     .05       0
  4880.9     .12       0  4899.2     .05       0  4994.5     .05       0
  5029.7     .05       0  5132.5     .12       0  5228.7     .05       0
Bank Sta=4994.5,5029.7
XS Rating Curve= 0 ,0
Exp/Cntr=0.3,0.1

Type RM Length L Ch R = 1 ,47000   ,500,500,500
BEGIN DESCRIPTION:
PECAN CREEK 94.0
END DESCRIPTION:
XS GIS Cut Line= 3
      2800955.68     10279753.11      2800563.65     10279479.79
       2800205.7     10279003.13
#Sta/Elev= 30
  4522.1 1215.56    4595 1205.89  4601.1 1206.05  4615.9 1202.32  4644.9 1200.74
  4680.6 1199.22  4687.4 1194.93  4702.3 1190.73  4758.8 1181.86    4819  1174.9
  4845.4 1170.64  4910.8 1166.22  4937.8 1160.91  4985.9 1158.07  4986.7 1157.57
  5021.1 1158.07  5024.4 1163.48  5038.9 1165.65  5068.1 1173.66  5082.7 1175.23
  5107.4  1174.5  5132.6 1176.56  5168.1 1177.78  5272.5 1185.47  5288.9  1186.4
  5303.5 1189.29  5338.9 1192.31  5403.4 1201.19    5437 1204.35  5596.1 1222.15
#Mann= 10 ,-1 , 0
  4522.1     .05       0  4644.9     .12       0  4758.8     .05       0
    4819     .12       0  4985.9     .07       0  5021.1     .12       0
  5107.4     .05       0  5132.6     .12       0  5272.5     .05       0
    5437     .12       0
Bank Sta=4985.9,5021.1
XS Rating Curve= 0 ,0
Exp/Cntr=0.3,0.1

Type RM Length L Ch R = 1 ,46500   ,473,473,473
BEGIN DESCRIPTION:
PECAN CREEK 93.0
END DESCRIPTION:
XS GIS Cut Line= 3
      2801255.69     10279353.12      2800878.92     10279093.24
       2800805.7     10278903.16
#Sta/Elev= 30
  4542.3 1209.47  4570.7 1206.17  4585.6 1202.78  4606.5 1199.75  4621.4 1199.09
  4673.7 1190.47    4687 1189.63  4736.7 1182.73  4773.1 1180.65  4800.6 1177.94
  4809.4 1176.82  4821.7 1173.17  4836.4 1171.82  4858.2 1167.85  4881.1 1165.85
  4887.1 1164.35  4937.9 1158.29  4979.8 1156.66  4981.3  1154.5    4982    1154
  5016.6  1154.5  5019.6 1158.22  5024.9 1160.25  5054.9 1163.58  5074.2 1162.88
  5079.5 1164.38  5085.9 1163.98  5096.6 1165.86  5103.9 1168.83  5203.7 1178.86
#Mann= 5 ,-1 , 0
  4542.3     .12       0  4673.7     .05       0  4981.3     .07       0
  5016.6     .05       0  5103.9     .05       0
Bank Sta=4981.3,5016.6
XS Rating Curve= 0 ,0
Exp/Cntr=0.3,0.1