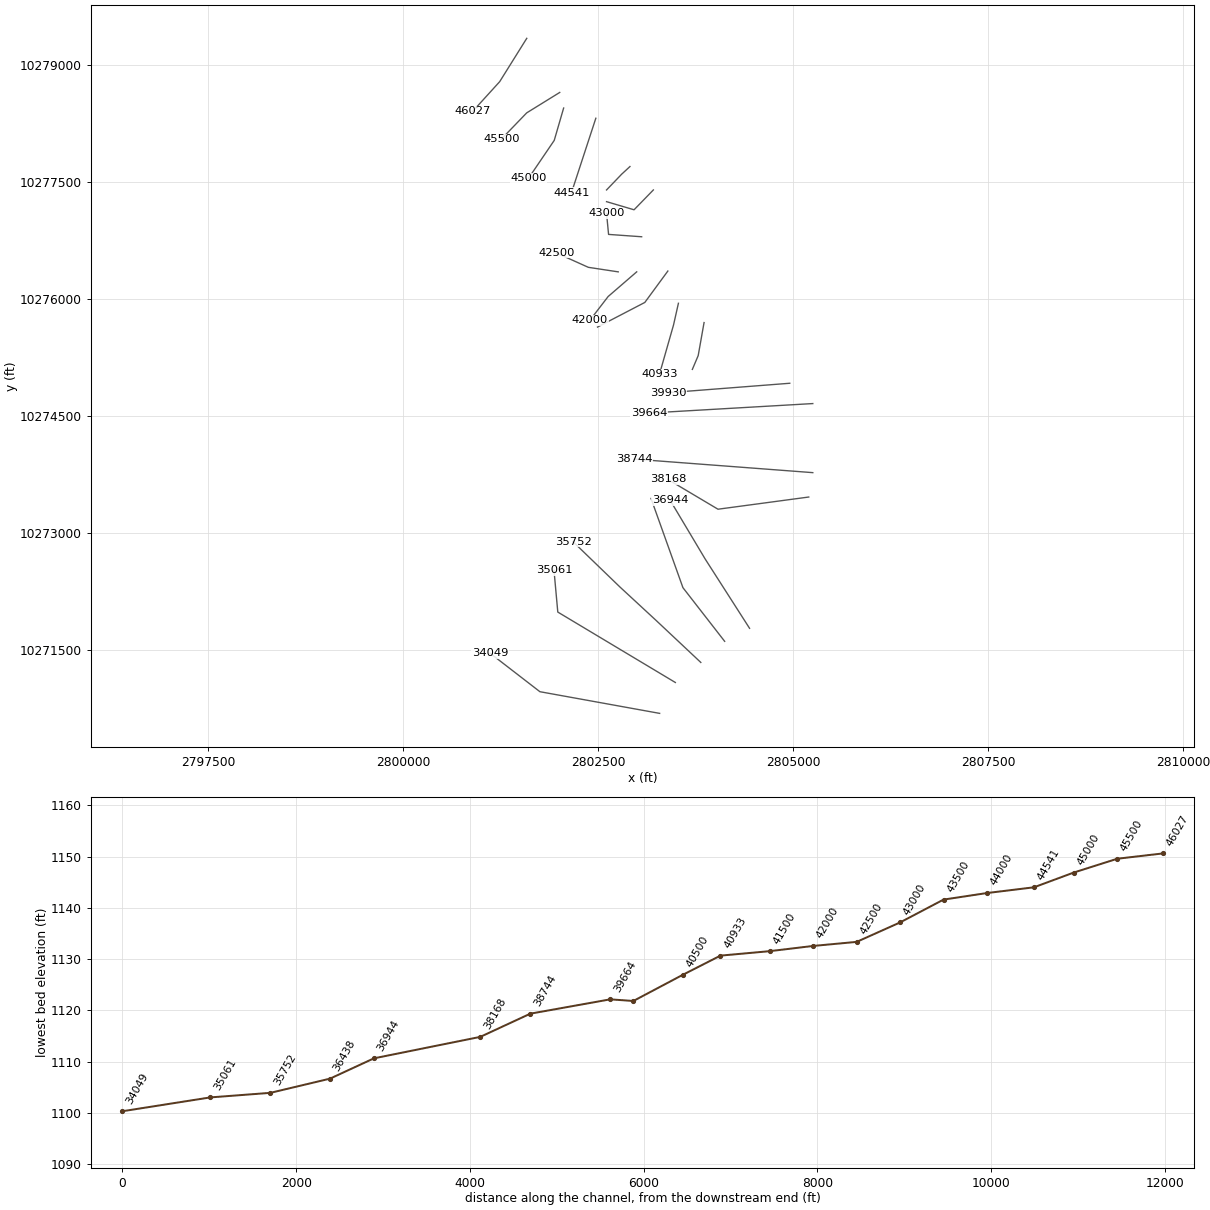
HEC-RAS study PECAN CREEK.prj: PECAN CREEK Base Level Engineering

--- PECAN CREEK.g01 (geometry) --- (continued)

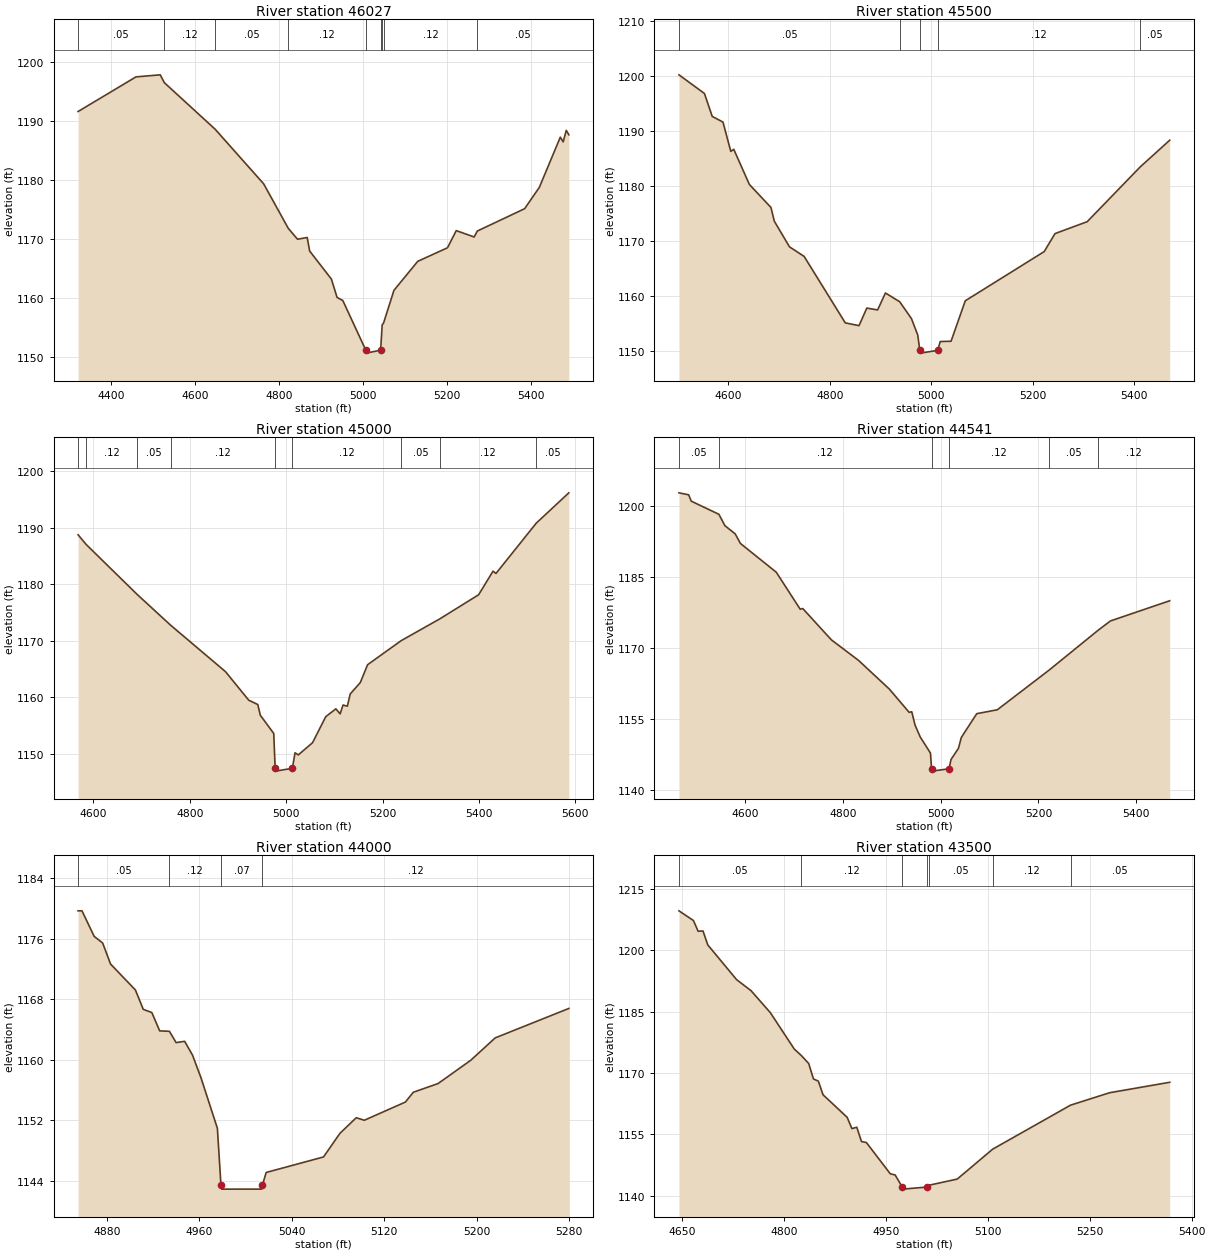
Type RM Length L Ch R = 1 ,46027   ,527,527,527
BEGIN DESCRIPTION:
Mapping XS 75dcb062
END DESCRIPTION:
XS GIS Cut Line= 3
      2801582.96     10279346.58      2801235.74     10278791.03
      2800889.61     10278410.28
#Sta/Elev= 30
  4320.6 1191.66  4458.6 1197.54  4516.4 1197.89  4526.2 1196.56  4647.2 1188.66
  4762.9 1179.39  4821.5 1171.84  4843.6 1169.98  4866.7 1170.27  4872.6 1167.97
  4924.4 1163.21  4937.9  1160.1  4951.6 1159.57  5006.4 1151.14  5007.1 1150.64
  5041.7 1151.14  5045.4 1155.42  5048.9 1155.78  5073.4 1161.29  5130.1 1166.22
  5201.1 1168.53    5222 1171.44  5264.6 1170.36  5272.2 1171.37  5384.9 1175.16
    5420 1178.78    5470 1187.31  5476.8 1186.51  5484.2 1188.46  5490.3 1187.71
#Mann= 9 ,-1 , 0
  4320.6     .05       0  4526.2     .12       0  4647.2     .05       0
  4821.5     .12       0  5006.4     .07       0  5041.7     .12       0
  5045.4     .05       0  5048.9     .12       0  5272.2     .05       0
Bank Sta=5006.4,5041.7
XS Rating Curve= 0 ,0
Exp/Cntr=0.3,0.1

Type RM Length L Ch R = 1 ,45500   ,500,500,500
BEGIN DESCRIPTION:
PECAN CREEK 91.0
END DESCRIPTION:
XS GIS Cut Line= 3
      2802005.66      10278653.1      2801582.55      10278391.4
      2801255.69     10278053.11
#Sta/Elev= 30
  4502.5 1200.26  4552.7 1196.87  4568.1 1192.69  4589.3 1191.66  4604.7 1186.33
  4610.6  1186.7  4641.4  1180.3  4683.9 1176.12  4690.6 1173.61  4720.5 1168.95
  4749.4  1167.2  4830.5 1155.11  4857.6  1154.6    4873  1157.8  4894.3 1157.46
  4909.7 1160.55  4937.9 1158.95    4961 1155.89  4973.5 1152.88  4977.5  1150.1
  4978.3  1149.6  5012.9  1150.1  5017.8 1151.71  5039.1 1151.76  5067.2 1159.13
  5222.8 1168.08  5244.2 1171.36  5307.7 1173.53  5411.9 1183.47  5470.4 1188.36
#Mann= 5 ,-1 , 0
  4502.5     .05       0  4937.9     .12       0  4977.5     .07       0
  5012.9     .12       0  5411.9     .05       0
Bank Sta=4977.5,5012.9
XS Rating Curve= 0 ,0
Exp/Cntr=0.3,0.1

Type RM Length L Ch R = 1 ,45000   ,459,459,459
BEGIN DESCRIPTION:
PECAN CREEK 90.0
END DESCRIPTION:
XS GIS Cut Line= 3
      2802055.69     10278453.12      2801935.13     10278038.29
      2801605.66     10277553.07
#Sta/Elev= 30
    4568 1188.76  4585.1 1187.02  4690.6  1178.2  4760.5 1172.72  4873.9 1164.53
  4922.1 1159.48    4941  1158.7  4946.2 1156.81  4974.1 1153.58    4977 1147.41
  4977.8 1146.91  5012.7 1147.41  5018.3 1150.16    5025 1149.78  5054.6 1151.94
    5082 1156.55    5103 1157.94  5111.9 1157.05  5117.9 1158.62  5126.8  1158.4
  5132.8 1160.57  5153.8  1162.6  5168.8 1165.75  5238.3    1170  5318.9 1173.88
  5399.3 1178.14  5429.2 1182.32  5435.3 1181.91  5518.9 1190.82  5586.5 1196.19
#Mann= 9 ,-1 , 0
    4568     .05       0  4585.1     .12       0  4690.6     .05       0
  4760.5     .12       0    4977     .07       0  5012.7     .12       0
  5238.3     .05       0  5318.9     .12       0  5518.9     .05       0
Bank Sta=4977,5012.7
XS Rating Curve= 0 ,0
Exp/Cntr=0.3,0.1

Type RM Length L Ch R = 1 ,44541   ,541,541,541
BEGIN DESCRIPTION:
Mapping XS ed938114
END DESCRIPTION:
XS GIS Cut Line= 2
      2802468.39     10278322.29      2802156.01     10277367.81
#Sta/Elev= 30
  4464.3 1202.89  4484.1 1202.47  4489.4 1201.13    4546 1198.35  4558.4 1195.93
  4579.2 1194.23  4590.2 1192.17  4663.4  1186.1  4712.4 1178.27  4717.7 1178.41
  4776.1  1171.8  4831.7 1167.45  4894.8 1161.38  4935.4 1156.45  4940.7 1156.58
  4947.4 1153.77    4958 1151.25    4979 1147.83  4981.2 1144.52  4982.1 1144.02
    5017 1144.52  5021.1 1146.49  5036.3 1148.85  5042.1 1151.14  5073.7 1156.17
  5115.8    1157  5222.4 1165.44  5322.2 1173.83  5347.3 1175.79  5468.6 1180.06
#Mann= 6 ,-1 , 0
  4464.3     .05       0    4546     .12       0  4981.2     .07       0
    5017     .12       0  5222.4     .05       0  5322.2     .12       0
Bank Sta=4981.2,5017
XS Rating Curve= 0 ,0
Exp/Cntr=0.3,0.1

Type RM Length L Ch R = 1 ,44000   ,500,500,500
BEGIN DESCRIPTION:
PECAN CREEK 88.0
END DESCRIPTION:
XS GIS Cut Line= 3
      2802905.69     10277703.12      2802799.18     10277604.88
      2802605.65     10277403.08
#Sta/Elev= 30
  4855.1 1179.67  4858.5 1179.67    4869  1176.3  4876.4 1175.41  4883.2 1172.64
  4904.7 1169.21  4911.5 1166.65  4918.9 1166.23  4925.7 1163.81  4934.1 1163.75
  4939.9 1162.26  4947.3 1162.43  4954.1  1160.6  4961.4 1157.62  4975.6 1150.94
  4978.7  1143.4  4979.5  1142.9  5013.7  1142.9  5014.5  1143.4  5017.8  1145.1
  5067.4 1147.15  5081.6 1150.27  5095.7 1152.33  5102.7    1152  5138.2  1154.4
  5145.1  1155.7  5166.5 1156.85  5194.8 1159.93  5215.9 1162.88  5279.6 1166.77
#Mann= 4 ,-1 , 0
  4855.1     .05       0  4934.1     .12       0  4978.7     .07       0
  5014.5     .12       0
Bank Sta=4978.7,5014.5
XS Rating Curve= 0 ,0
Exp/Cntr=0.3,0.1

Type RM Length L Ch R = 1 ,43500   ,500,500,500
BEGIN DESCRIPTION:
PECAN CREEK 87.0
END DESCRIPTION:
XS GIS Cut Line= 3
      2803205.72     10277403.15      2802958.33     10277148.82
      2802605.72      10277253.1
#Sta/Elev= 30
  4645.2 1209.63  4666.5 1207.26  4673.4 1204.64  4680.6 1204.71  4687.6 1201.31
    4730 1192.82  4751.3 1190.12  4779.6 1184.77  4814.9 1175.87  4825.2 1174.29
  4836.2 1172.32  4843.2 1168.55  4850.4 1168.01  4857.3 1164.68  4892.8 1159.17
  4899.8 1156.41    4907 1156.74  4913.9 1153.25  4921.1 1153.01  4956.4 1145.35
  4963.5 1145.08  4973.9 1142.12  4974.7 1141.62  5009.8 1142.12  5012.8 1142.55
  5054.9 1144.08    5107 1151.38  5221.7 1162.14  5279.3 1165.18  5367.7 1167.73
#Mann= 7 ,-1 , 0
  4645.2     .05       0  4825.2     .12       0  4973.9     .07       0
  5009.8     .12       0  5012.8     .05       0    5107     .12       0
  5221.7     .05       0
Bank Sta=4973.9,5009.8
XS Rating Curve= 0 ,0
Exp/Cntr=0.3,0.1

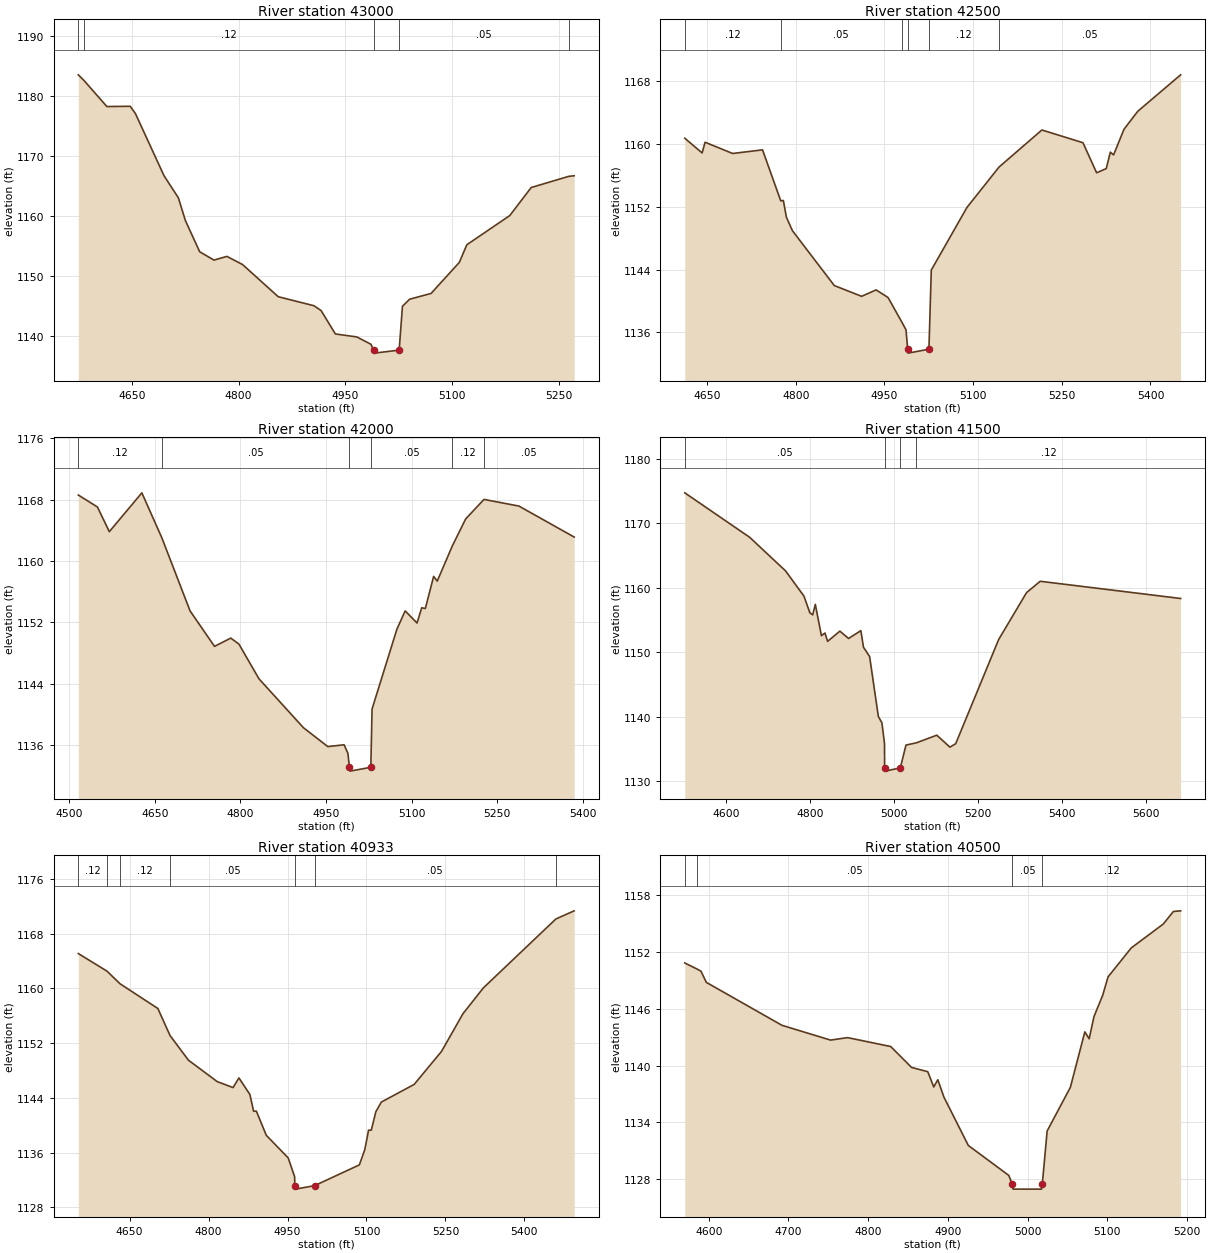
Type RM Length L Ch R = 1 ,43000   ,500,500,500
BEGIN DESCRIPTION:
PECAN CREEK 86.0
END DESCRIPTION:
XS GIS Cut Line= 3
      2803055.68     10276803.11      2802631.65     10276833.25
      2802605.69      10277103.1
#Sta/Elev= 30
  4574.9 1183.59  4582.6 1182.68    4615  1178.3  4647.8 1178.34  4655.1 1177.12
  4695.2 1166.76  4715.3 1163.09  4725.3 1159.26  4745.3 1154.07  4765.4 1152.68
  4783.5  1153.3  4805.5 1151.94  4855.6 1146.57  4905.7 1145.07  4915.8 1144.26
  4935.8 1140.36  4965.9 1139.86  4985.9 1138.63  4989.5 1137.66  4990.4 1137.16
  5025.4 1137.66    5030 1144.97    5040 1146.15  5070.2 1147.12  5109.9  1152.3
  5120.4 1155.24  5180.7 1160.11  5210.8 1164.79  5263.4 1166.65  5271.1 1166.75
#Mann= 5 ,-1 , 0
  4574.9     .05       0  4582.6     .12       0  4989.5     .07       0
  5025.4     .05       0  5263.4     .12       0
Bank Sta=4989.5,5025.4
XS Rating Curve= 0 ,0
Exp/Cntr=0.3,0.1

Type RM Length L Ch R = 1 ,42500   ,500,500,500
BEGIN DESCRIPTION:
PECAN CREEK 85.0
END DESCRIPTION:
XS GIS Cut Line= 3
      2802755.68     10276353.11      2802372.28     10276411.33
      2801960.97     10276596.33
#Sta/Elev= 30
  4612.2 1160.71  4641.5 1158.84  4646.5  1160.2  4693.1 1158.77  4743.7 1159.23
  4774.6 1152.73  4778.9 1152.79  4784.1 1150.66  4794.3 1148.94  4865.1 1141.96
  4911.3 1140.59  4935.9 1141.41  4956.1 1140.43  4978.8 1137.39  4986.4 1136.33
  4989.3 1133.86  4990.1 1133.36  5025.2 1133.86  5029.2 1143.93  5089.6 1151.91
  5143.9 1157.05  5216.3 1161.76  5285.8 1160.14  5308.9 1156.31  5325.2 1156.85
  5332.1 1158.94  5337.6 1158.59  5355.2 1161.85  5378.4 1164.13    5451 1168.78
#Mann= 6 ,-1 , 0
  4612.2     .12       0  4774.6     .05       0  4978.8     .12       0
  4989.3     .07       0  5025.2     .12       0  5143.9     .05       0
Bank Sta=4989.3,5025.2
XS Rating Curve= 0 ,0
Exp/Cntr=0.3,0.1

Type RM Length L Ch R = 1 ,42000   ,500,500,500
BEGIN DESCRIPTION:
PECAN CREEK 84.0
END DESCRIPTION:
XS GIS Cut Line= 3
      2802992.22     10276353.25       2802626.1       10276037.
      2802391.52     10275731.72
#Sta/Elev= 30
  4516.2  1168.6  4549.7 1167.04  4570.5 1163.82  4627.5 1168.89  4662.7 1162.99
    4712 1153.48  4754.8 1148.85  4783.3 1149.93  4797.6 1149.15  4832.7 1144.62
  4910.6 1138.24  4953.4 1135.77  4981.9 1136.01  4988.5  1134.9  4991.3 1133.07
  4992.3 1132.57  5028.7 1133.07  5030.9 1140.68  5074.4 1151.09  5088.9 1153.48
  5109.7  1151.9  5117.9 1153.89  5124.2 1153.79  5138.8 1157.98  5145.1 1157.37
  5171.4 1161.94  5194.9 1165.48    5227 1168.03  5288.3 1167.16    5385 1163.12
#Mann= 6 ,-1 , 0
  4516.2     .12       0  4662.7     .05       0  4991.3     .05       0
  5028.7     .05       0  5171.4     .12       0    5227     .05       0
Bank Sta=4991.3,5028.7
XS Rating Curve= 0 ,0
Exp/Cntr=0.3,0.1

Type RM Length L Ch R = 1 ,41500   ,567,567,567
BEGIN DESCRIPTION:
PECAN CREEK 83.0
END DESCRIPTION:
XS GIS Cut Line= 3
      2803391.53     10276363.67      2803096.28     10275961.15
      2802489.72     10275645.43
#Sta/Elev= 30
  4500.8 1174.75  4655.5 1167.85  4741.1 1162.64  4785.1 1158.72  4799.1 1156.14
    4806  1155.8  4812.2 1157.44  4826.8 1152.57  4835.3 1152.99  4841.5 1151.69
  4870.8 1153.28  4891.6 1152.14  4920.9 1153.36  4927.1 1150.79  4941.8 1149.33
  4962.6 1140.03  4971.1 1139.05  4977.3 1135.83  4977.6 1132.05  4978.5 1131.55
    5015 1132.05  5028.5 1135.59  5053.6 1135.95  5102.1 1137.13  5133.4 1135.27
  5147.2 1135.81  5249.6 1151.97  5316.3 1159.27  5348.8 1161.02  5683.8 1158.35
#Mann= 4 ,-1 , 0
  4500.8     .05       0  4977.6     .05       0    5015     .05       0
  5053.6     .12       0
Bank Sta=4977.6,5015
XS Rating Curve= 0 ,0
Exp/Cntr=0.3,0.1

Type RM Length L Ch R = 1 ,40933   ,433,433,433
BEGIN DESCRIPTION:
Mapping XS d416f65e
END DESCRIPTION:
XS GIS Cut Line= 3
      2803526.96     10275950.53      2803464.46     10275672.71
       2803283.9     10275040.76
#Sta/Elev= 30
  4552.6 1165.08  4607.1 1162.51  4631.8 1160.67  4703.7 1157.06  4726.9  1153.1
  4761.8 1149.51  4816.5 1146.38  4846.6 1145.51  4857.7 1146.92  4878.5 1144.51
  4885.6 1142.05  4890.8 1142.07  4909.7 1138.54  4951.3 1135.24  4963.6 1132.48
  4963.8 1131.18  4964.7 1130.68  5001.3 1131.18  5086.5 1134.22  5096.9 1136.46
    5104 1139.29  5109.2 1139.29  5117.8 1141.97  5128.2 1143.39  5190.6 1145.97
  5242.6 1150.79  5283.4  1156.3  5322.4 1160.09  5459.9 1170.13  5494.6 1171.32
#Mann= 7 ,-1 , 0
  4552.6     .12       0  4607.1     .05       0  4631.8     .12       0
  4726.9     .05       0  4963.8     .05       0  5001.3     .05       0
  5459.9     .12       0
Bank Sta=4963.8,5001.3
XS Rating Curve= 0 ,0
Exp/Cntr=0.3,0.1

Type RM Length L Ch R = 1 ,40500   ,570,570,570
BEGIN DESCRIPTION:
PECAN CREEK 81.0
END DESCRIPTION:
XS GIS Cut Line= 3
      2803855.68     10275703.11      2803780.53     10275279.73
      2803705.69     10275103.13
#Sta/Elev= 30
    4570 1150.84  4585.8 1150.18  4590.3 1149.97    4597 1148.79  4691.9 1144.25
  4752.8 1142.69  4774.2 1142.95  4828.2 1142.01  4854.4  1139.8  4874.7 1139.35
  4882.2 1137.74  4887.3  1138.5    4895 1136.66  4925.5 1131.56  4976.3 1128.39
  4980.8 1127.44  4981.7 1126.94  5017.3 1126.94  5018.3 1127.44  5024.4 1133.08
  5053.5 1137.69  5071.7 1143.56  5077.1 1142.83  5083.2 1145.19  5094.1 1147.43
  5100.8 1149.37  5129.9 1152.43  5170.1 1154.96  5182.7 1156.28  5191.8 1156.35
#Mann= 4 ,-1 , 0
    4570     .12       0  4585.8     .05       0  4980.8     .05       0
  5018.3     .12       0
Bank Sta=4980.8,5018.3
XS Rating Curve= 0 ,0
Exp/Cntr=0.3,0.1

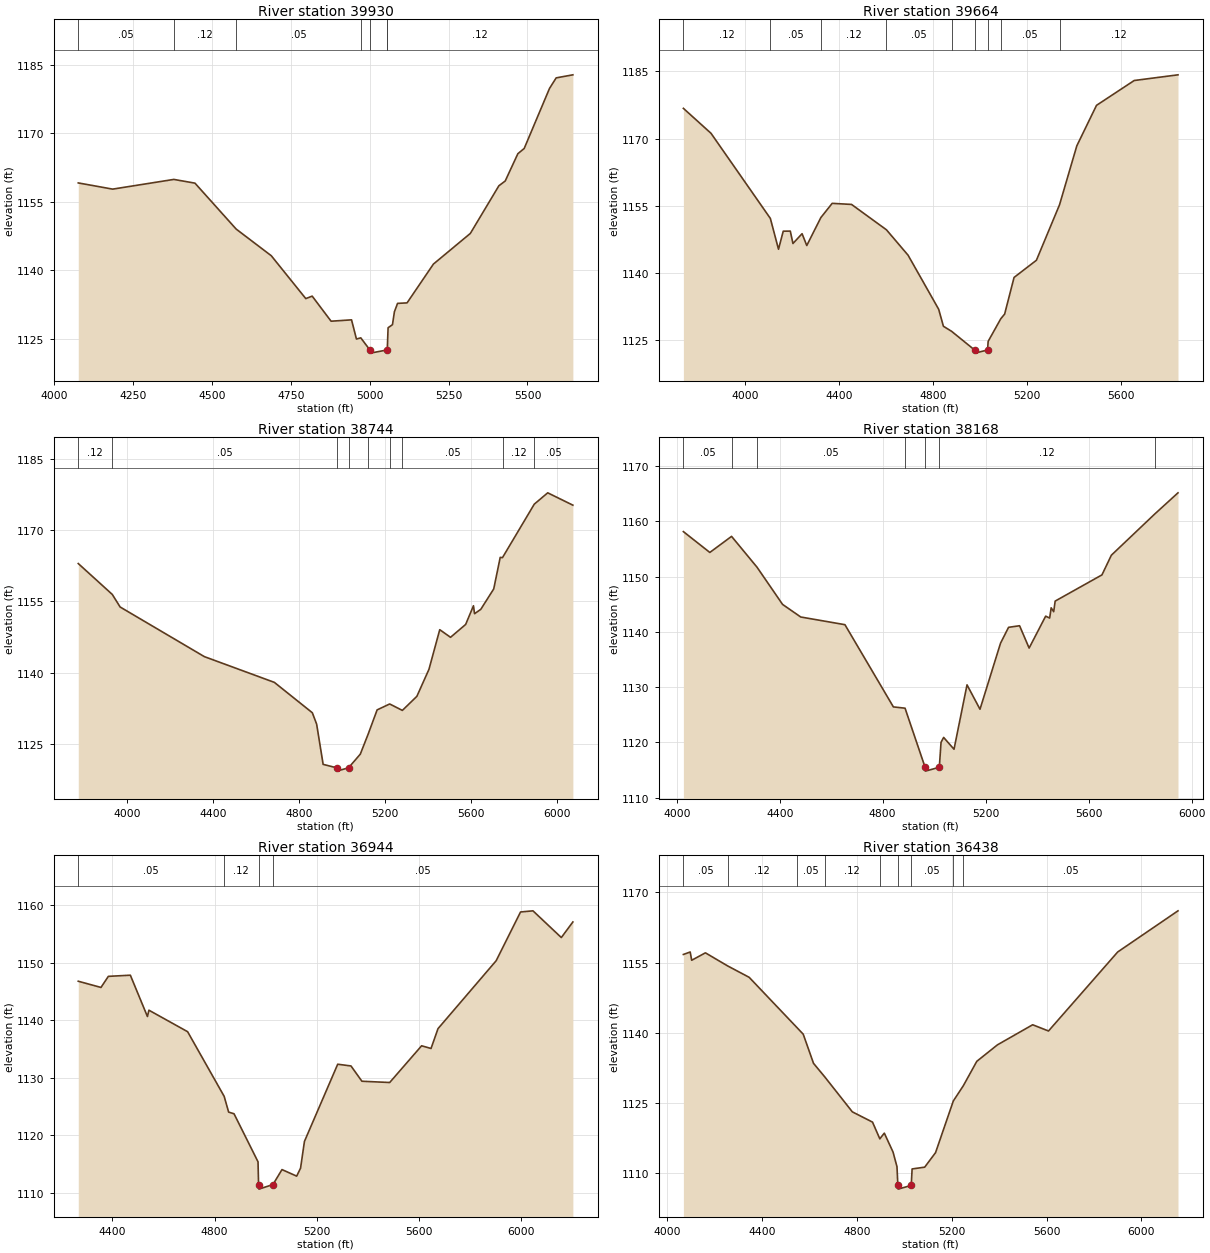
Type RM Length L Ch R = 1 ,39930   ,266,266,266
BEGIN DESCRIPTION:
Mapping XS 039a20b0
END DESCRIPTION:
XS GIS Cut Line= 2
      2804954.39     10274925.23      2803391.91      10274803.7
#Sta/Elev= 30
  4076.6 1159.15  4185.6 1157.79  4379.4 1159.92  4446.4  1159.1  4576.9 1149.03
  4688.2 1143.18  4797.5 1133.78  4817.8 1134.32  4877.7 1128.82  4942.5 1129.12
    4958 1124.91  4971.8 1125.17  5000.6 1122.52  5001.8 1121.82  5055.7 1122.52
  5056.3 1123.64  5058.3 1127.39  5072.2 1128.06  5078.3 1130.88  5088.3 1132.73
  5118.4 1132.84  5201.9 1141.35    5319 1148.08  5409.3 1158.52  5429.4 1159.57
  5469.5 1165.56  5489.6 1166.71  5569.8 1179.88  5590.9 1182.19  5643.8 1182.86
#Mann= 7 ,-1 , 0
  4076.6     .05       0  4379.4     .12       0  4576.9     .05       0
  4971.8     .12       0  5000.6     .07       0  5055.7     .12       0
  5056.3     .12       0
Bank Sta=5000.6,5055.7
XS Rating Curve= 0 ,0
Exp/Cntr=0.3,0.1

Type RM Length L Ch R = 1 ,39664   ,920,920,920
BEGIN DESCRIPTION:
Mapping XS 36193bd1
END DESCRIPTION:
XS GIS Cut Line= 2
      2805249.54     10274664.81      2803149.75     10274543.33
#Sta/Elev= 30
  3739.1 1176.76  3856.6 1171.19  4108.9  1152.2  4143.6 1145.32  4163.7 1149.35
  4193.7 1149.37    4205  1146.6  4243.8 1148.79  4263.8 1146.15  4323.6 1152.38
  4371.8 1155.56  4454.2 1155.32  4602.6 1149.66  4694.6 1143.99  4824.8 1131.92
  4844.8 1128.14  4879.8    1127  4977.5 1122.84  4978.7 1122.14  5032.6 1122.84
  5035.1 1124.76  5088.8 1129.81  5105.2 1130.85  5145.3 1139.03  5240.3 1142.86
  5338.7 1155.25  5412.1 1168.39  5495.9 1177.43  5656.2 1182.97  5842.4 1184.24
#Mann= 9 ,-1 , 0
  3739.1     .12       0  4108.9     .05       0  4323.6     .12       0
  4602.6     .05       0  4879.8     .12       0  4977.5     .07       0
  5032.6     .12       0  5088.8     .05       0  5338.7     .12       0
Bank Sta=4977.5,5032.6
XS Rating Curve= 0 ,0
Exp/Cntr=0.3,0.1

Type RM Length L Ch R = 1 ,38744   ,576,576,576
BEGIN DESCRIPTION:
Mapping XS 2e6a48e7
END DESCRIPTION:
XS GIS Cut Line= 2
      2805249.49     10273779.39      2802959.25     10273952.89
#Sta/Elev= 30
  3774.9 1162.96    3933 1156.46  3969.3 1153.83  4360.4  1143.4  4685.5 1137.99
  4861.8 1131.61  4881.9  1129.2    4912 1120.76  4974.6 1120.04  4975.8 1119.34
  5029.9 1120.04  5084.6 1122.91  5121.7 1127.19  5162.7 1132.21  5221.1 1133.45
  5279.9  1132.1  5347.3 1135.06  5403.4 1140.73  5453.5 1149.06  5503.6 1147.46
  5573.8 1150.16  5610.1 1154.09  5615.1 1152.42    5644 1153.33  5704.2 1157.63
  5734.3 1164.25  5744.9 1164.21  5892.5 1175.44  5954.9 1177.82  6071.7 1175.23
#Mann= 9 ,-1 , 0
  3774.9     .12       0    3933     .05       0  4974.6     .03       0
  5029.9     .05       0  5121.7     .05       0  5221.1     .12       0
  5279.9     .05       0  5744.9     .12       0  5892.5     .05       0
Bank Sta=4974.6,5029.9
XS Rating Curve= 0 ,0
Exp/Cntr=0.3,0.1

Type RM Length L Ch R = 1 ,38168   ,1224,1224,1224
BEGIN DESCRIPTION:
Mapping XS d9a59213
END DESCRIPTION:
XS GIS Cut Line= 3
      2805197.46      10273466.9      2804034.23     10273310.64
      2803391.88     10273692.58
#Sta/Elev= 30
    4026 1158.15  4128.7 1154.38  4213.1 1157.29  4312.2  1151.7  4411.2 1144.98
  4481.8  1142.7  4653.4 1141.31  4841.6 1126.43  4886.9  1126.2  4964.7 1115.51
  4965.9 1114.81    5020 1115.51  5026.7 1120.02  5036.8 1120.91  5077.1 1118.77
  5127.6 1130.42    5178 1126.01  5257.7 1137.95  5288.9 1140.83  5331.7 1141.12
  5368.8 1137.08    5433 1142.85  5448.6 1142.51  5454.4 1144.36  5464.2 1143.66
    5470 1145.58  5651.7 1150.32  5688.2 1153.88  5855.9  1161.3    5947 1165.17
#Mann= 7 ,-1 , 0
    4026     .05       0  4213.1     .12       0  4312.2     .05       0
  4886.9     .12       0  4964.7     .07       0    5020     .12       0
  5855.9     .05       0
Bank Sta=4964.7,5020
XS Rating Curve= 0 ,0
Exp/Cntr=0.3,0.1

Type RM Length L Ch R = 1 ,36944   ,506,506,506
BEGIN DESCRIPTION:
Mapping XS 0b04e56c
END DESCRIPTION:
XS GIS Cut Line= 3
      2804439.08     10271783.93      2803869.65     10272672.79
      2803418.74     10273428.93
#Sta/Elev= 30
  4266.2 1146.79  4355.1 1145.71    4384 1147.64  4470.1 1147.84  4536.9 1140.65
  4542.8 1141.75  4694.2 1138.01  4837.2 1126.77  4854.8 1124.02  4875.9 1123.73
  4969.8 1115.37    4972 1111.42  4973.3 1110.62  5028.3 1111.42  5063.6 1114.02
  5121.1 1112.88  5136.3 1114.27  5151.5 1118.92  5281.7 1132.35  5333.7 1132.05
  5376.5 1129.39  5485.2 1129.17  5610.1 1135.56    5647 1135.09  5674.3 1138.54
    5902 1150.36  5997.4 1158.84    6046 1159.04    6157 1154.39  6202.2  1157.1
#Mann= 4 ,-1 , 0
  4266.2     .05       0  4837.2     .12       0    4972     .07       0
  5028.3     .05       0
Bank Sta=4972,5028.3
XS Rating Curve= 0 ,0
Exp/Cntr=0.3,0.1

Type RM Length L Ch R = 1 ,36438   ,686,686,686
BEGIN DESCRIPTION:
Mapping XS 1ae94b5c
END DESCRIPTION:
XS GIS Cut Line= 3
      2804119.67     10271617.21      2803584.92     10272304.74
      2803175.63     10273449.36
#Sta/Elev= 30
  4067.7 1156.76  4096.4 1157.29  4102.7 1155.52  4160.6 1157.11  4254.6 1154.31
  4345.2 1151.88  4546.2 1141.18  4573.3 1139.73  4616.7 1133.51  4663.6 1130.65
  4780.5 1123.15  4865.6 1120.96  4896.4 1117.39  4915.3 1118.61  4952.1 1114.58
  4968.8 1111.43  4972.5 1107.45  4973.8 1106.65  5028.9 1107.45  5032.6 1110.96
  5085.7 1111.34  5131.5 1114.44  5206.4 1125.47  5248.8 1128.74  5305.5 1133.94
  5392.6 1137.46  5541.2 1141.75    5608 1140.42  5899.9 1157.29  6154.3 1166.08
#Mann= 9 ,-1 , 0
  4067.7     .05       0  4254.6     .12       0  4546.2     .05       0
  4663.6     .12       0  4896.4     .05       0  4972.5     .05       0
  5028.9     .05       0  5206.4     .12       0  5248.8     .05       0
Bank Sta=4972.5,5028.9
XS Rating Curve= 0 ,0
Exp/Cntr=0.3,0.1

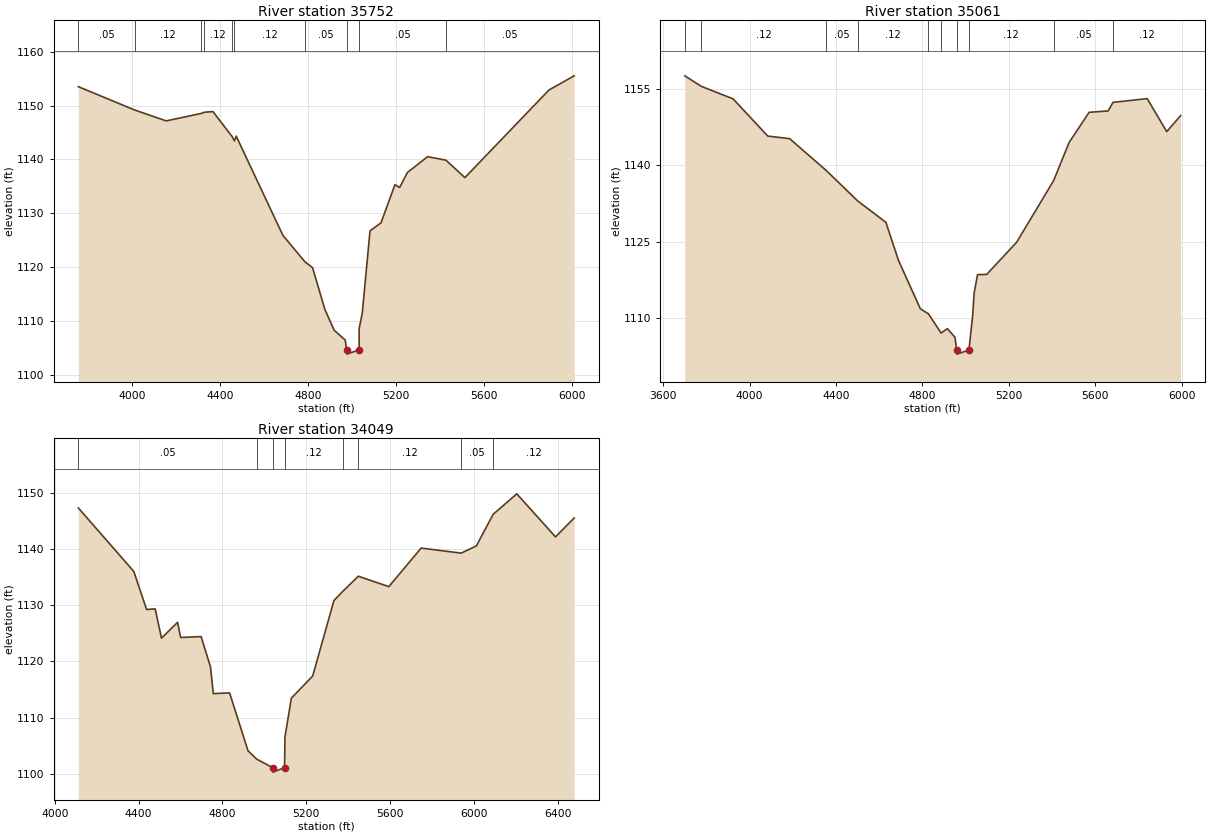
Type RM Length L Ch R = 1 ,35752   ,691,691,691
BEGIN DESCRIPTION:
Mapping XS 21f8454f
END DESCRIPTION:
XS GIS Cut Line= 4
       2803814.1      10271346.4       2803237.7     10271888.07
      2802779.37     10272311.68      2802175.21     10272895.01
#Sta/Elev= 30
  3754.5  1153.5  4010.7 1149.17  4154.2 1147.15  4313.1 1148.53  4327.2 1148.75
  4366.6 1148.88  4454.4 1144.22  4464.4 1143.45  4472.6 1144.32  4684.7 1125.92
    4785 1121.01  4819.6 1119.92  4875.8 1112.17  4918.3 1108.29  4968.2  1106.5
  4975.1 1104.68  4976.4 1103.88  5031.6 1104.68  5031.7 1108.63  5045.9 1111.53
    5081 1126.75  5130.9 1128.23  5194.4 1135.32  5215.8 1134.79    5251 1137.57
  5342.8 1140.51  5426.3 1139.86  5512.6 1136.63  5894.6 1152.87  6009.4 1155.51
#Mann= 10 ,-1 , 0
  3754.5     .05       0  4010.7     .12       0  4313.1     .05       0
  4327.2     .12       0  4454.4     .05       0  4464.4     .12       0
    4785     .05       0  4975.1     .07       0  5031.6     .05       0
  5426.3     .05       0
Bank Sta=4975.1,5031.6
XS Rating Curve= 0 ,0
Exp/Cntr=0.3,0.1

Type RM Length L Ch R = 1 ,35061   ,1012,1012,1012
BEGIN DESCRIPTION:
Mapping XS 86f36693
END DESCRIPTION:
XS GIS Cut Line= 3
      2803487.67     10271089.48      2801980.76     10271992.24
      2801932.14       10272527.
#Sta/Elev= 30
  3700.7 1157.58    3777 1155.52  3924.5 1153.05  4084.5 1145.76  4185.6 1145.26
  4355.1 1139.01  4500.4 1133.04  4630.9 1128.85  4689.2 1121.38  4790.3 1111.89
  4827.9 1110.89  4886.3 1107.13  4915.4 1107.99  4950.3  1106.3  4958.5 1103.79
  4959.8 1102.99    5015 1103.79  5031.9 1110.33  5039.2 1114.98  5054.8 1118.58
  5097.5 1118.63  5235.6 1124.93    5407 1137.03  5478.3 1144.49  5571.1 1150.43
    5659 1150.69  5681.5 1152.37  5839.8 1153.11  5930.1 1146.63  5994.3 1149.78
#Mann= 10 ,-1 , 0
  3700.7     .05       0    3777     .12       0  4355.1     .05       0
  4500.4     .12       0  4827.9     .05       0  4886.3     .12       0
  4958.5     .07       0    5015     .12       0    5407     .05       0
  5681.5     .12       0
Bank Sta=4958.5,5015
XS Rating Curve= 0 ,0
Exp/Cntr=0.3,0.1

Type RM Length L Ch R = 1 ,34049   ,730,730,730
BEGIN DESCRIPTION:
Mapping XS 6d287095
END DESCRIPTION:
XS GIS Cut Line= 3
      2803286.27     10270693.63      2801751.59      10270971.4
      2801112.73     10271464.43
#Sta/Elev= 30
  4112.1 1147.29  4376.9 1135.99  4437.9 1129.23  4478.9 1129.33    4509 1124.12
  4585.8 1126.94  4600.5 1124.24  4697.9 1124.41  4742.8 1119.04  4756.4 1114.26
  4834.2 1114.38    4922 1104.09  4963.2 1102.61  5039.7 1101.09  5040.9 1100.29
  5096.3 1101.09  5098.5 1106.58  5128.9 1113.45  5230.6 1117.38  5332.2 1130.82
  5373.3 1132.41  5448.4 1135.14  5594.2 1133.29  5748.4 1140.15  5939.6 1139.25
    6012 1140.53    6092 1146.15  6204.9  1149.8  6389.7 1142.14  6478.7  1145.5
#Mann= 8 ,-1 , 0
  4112.1     .05       0  4963.2     .12       0  5039.7     .07       0
  5096.3     .12       0  5373.3     .05       0  5448.4     .12       0
  5939.6     .05       0    6092     .12       0
Bank Sta=5039.7,5096.3
XS Rating Curve= 0 ,0
Exp/Cntr=0.3,0.1