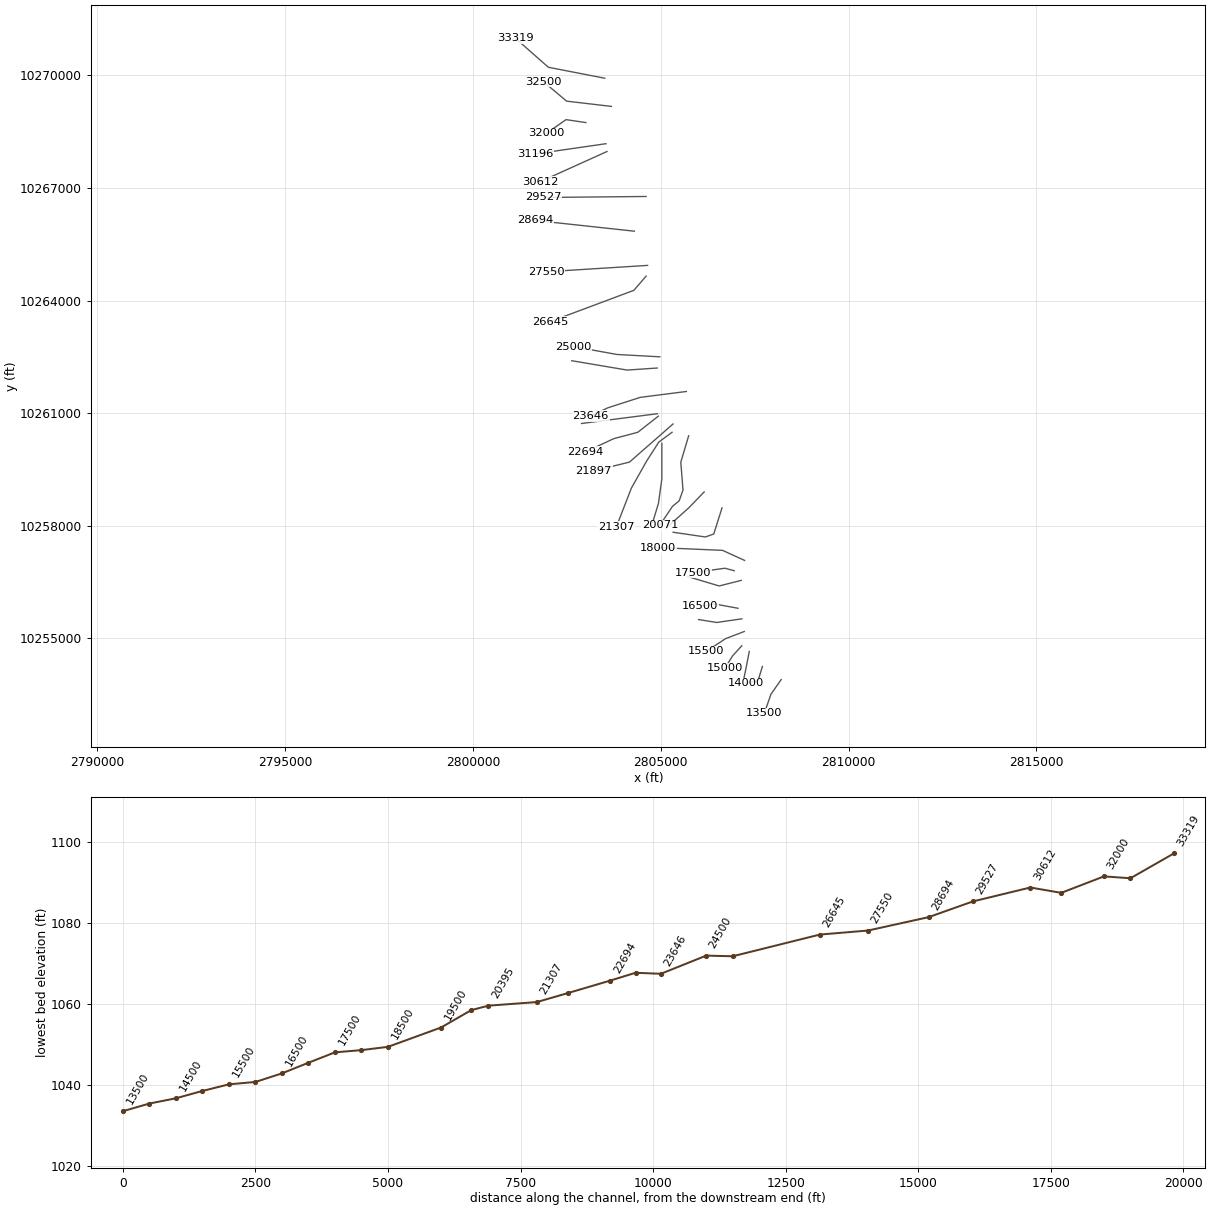
HEC-RAS study PECAN CREEK.prj: PECAN CREEK Base Level Engineering

--- PECAN CREEK.g01 (geometry) --- (continued)

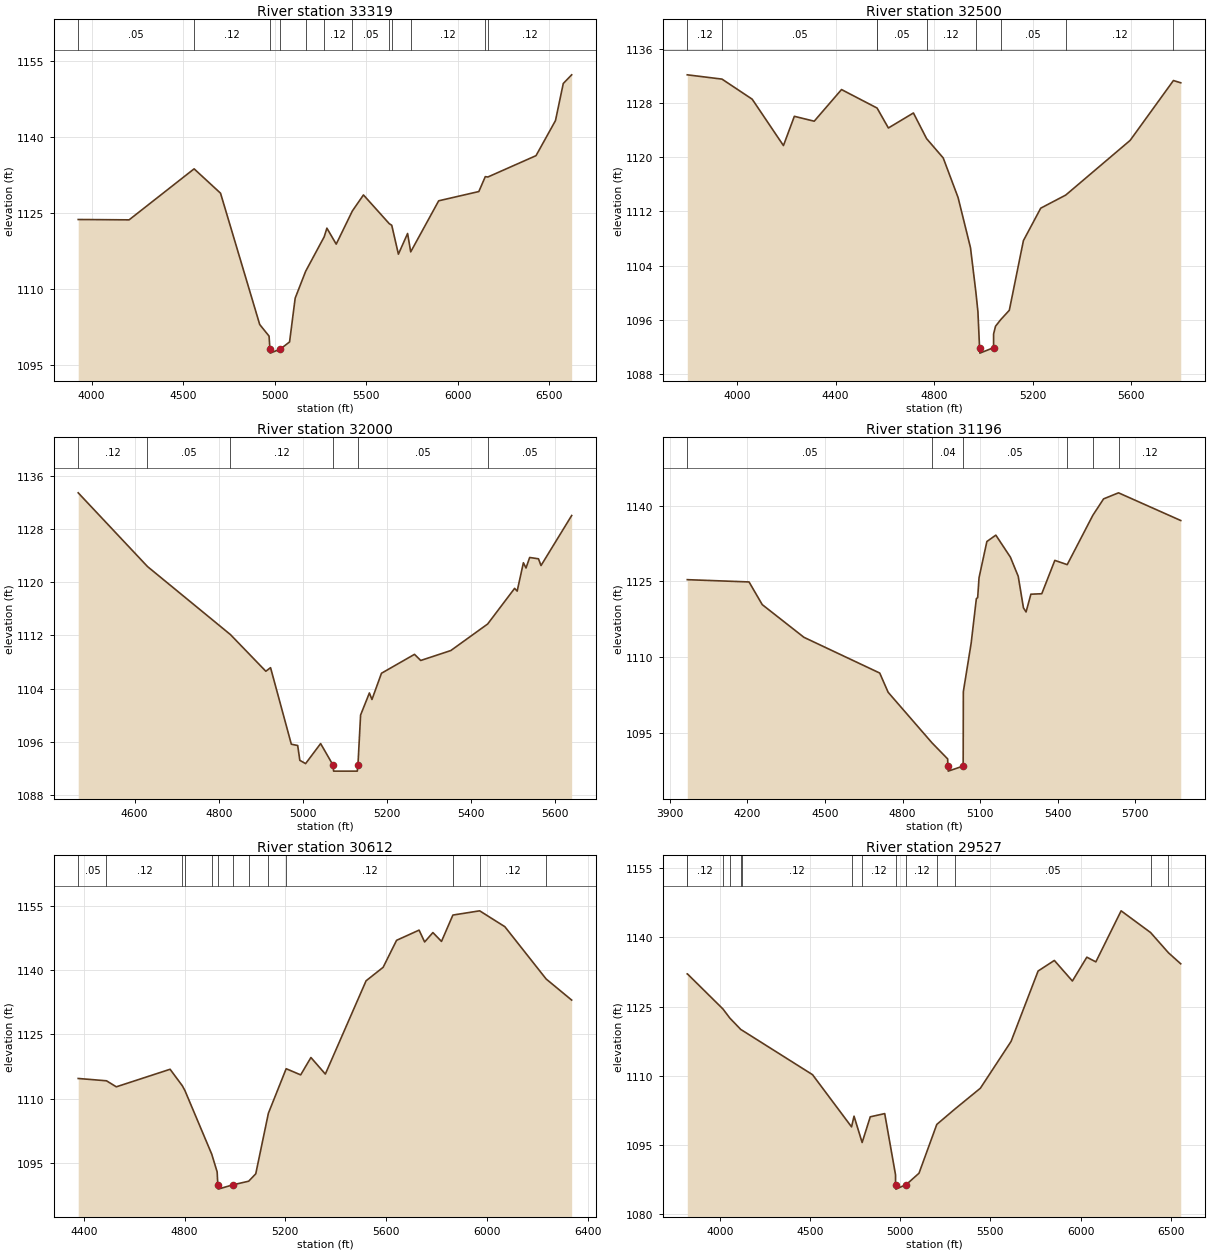
Type RM Length L Ch R = 1 ,33319   ,819,819,819
BEGIN DESCRIPTION:
Mapping XS b3e53869
END DESCRIPTION:
XS GIS Cut Line= 3
      2803508.51     10269923.35      2802008.53     10270215.02
      2801133.52     10270985.86
#Sta/Elev= 30
    3927 1123.66  4204.9 1123.59  4559.8 1133.66  4704.1 1128.85    4918 1102.93
    4969 1100.64  4973.9 1098.08  4975.2 1097.28  5030.6 1098.08    5081 1099.49
  5111.6 1108.13  5168.7 1113.43  5270.1 1120.25  5284.8 1121.95  5335.7  1118.8
  5423.9 1125.35  5484.4 1128.51  5625.2 1122.84  5638.9 1122.52  5675.2 1116.82
  5725.4  1120.9  5742.4 1117.27  5895.2 1127.35  6114.4 1129.18  6149.6 1132.12
  6163.7 1132.05  6426.5 1136.26  6532.8 1143.18  6575.4 1150.51  6621.2 1152.22
#Mann= 12 ,-1 , 0
    3927     .05       0  4559.8     .12       0  4973.9     .07       0
  5030.6     .12       0  5168.7     .05       0  5270.1     .12       0
  5423.9     .05       0  5625.2     .12       0  5638.9     .05       0
  5742.4     .12       0  6149.6     .05       0  6163.7     .12       0
Bank Sta=4973.9,5030.6
XS Rating Curve= 0 ,0
Exp/Cntr=0.3,0.1

Type RM Length L Ch R = 1 ,32500   ,500,500,500
BEGIN DESCRIPTION:
PECAN CREEK 65.0
END DESCRIPTION:
XS GIS Cut Line= 3
      2803687.37     10269172.48      2802493.27     10269312.68
      2801880.67     10269828.12
#Sta/Elev= 30
  3797.7 1132.13  3938.6  1131.5  4061.2 1128.54    4188 1121.71  4232.3 1126.02
  4312.9  1125.3  4423.7 1129.96  4567.9 1127.24  4569.1 1127.17  4613.9  1124.3
  4715.6 1126.51    4769 1122.73  4836.5 1119.89  4896.9 1114.05  4947.2 1106.67
    4969 1100.15  4977.4 1097.24    4984 1091.94  4985.3 1091.14  5040.9 1091.94
    5041 1093.96  5048.8  1095.1  5069.6 1096.06  5104.8 1097.45    5162 1107.71
  5232.3 1112.49  5333.8 1114.42  5595.1 1122.47  5770.9 1131.29  5800.6 1130.96
#Mann= 9 ,-1 , 0
  3797.7     .12       0  3938.6     .05       0  4567.9     .12       0
  4569.1     .05       0    4769     .12       0    4969     .07       0
  5069.6     .05       0  5333.8     .12       0  5770.9     .05       0
Bank Sta=4984,5040.9
XS Rating Curve= 0 ,0
Exp/Cntr=0.3,0.1

Type RM Length L Ch R = 1 ,32000   ,804,804,804
BEGIN DESCRIPTION:
PECAN CREEK 64.0
END DESCRIPTION:
XS GIS Cut Line= 3
      2803006.77     10268741.93      2802478.49     10268819.93
      2801955.65     10268453.09
#Sta/Elev= 30
    4466  1133.4  4630.6 1122.33  4827.9  1112.1  4911.9  1106.6  4923.1 1107.14
  4972.5 1095.64  4987.6 1095.45  4992.7 1093.22  5006.4 1092.73  5042.1 1095.74
  5071.6  1092.5    5073  1091.6  5129.3  1091.6  5130.8  1092.5  5137.1 1100.03
    5158 1103.34  5164.1 1102.36  5186.7  1106.3  5265.2 1109.14    5280 1108.22
  5351.5 1109.71  5439.1  1113.7  5503.1 1119.05  5509.2 1118.64    5524  1122.9
  5530.2 1122.11  5538.9 1123.69  5559.8 1123.49  5565.9 1122.48  5638.7 1129.99
#Mann= 6 ,-1 , 0
    4466     .12       0  4630.6     .05       0  4827.9     .12       0
  5071.6     .04       0  5130.8     .05       0  5439.1     .05       0
Bank Sta=5071.6,5130.8
XS Rating Curve= 0 ,0
Exp/Cntr=0.3,0.1

Type RM Length L Ch R = 1 ,31196   ,584,584,584
BEGIN DESCRIPTION:
Mapping XS b60f0e82
END DESCRIPTION:
XS GIS Cut Line= 2
        2803542.       10268179.       2801653.9     10267905.55
#Sta/Elev= 30
  3967.5 1125.36  4206.3 1124.91  4257.3 1120.43  4418.5 1113.97  4711.5 1106.91
    4744 1103.11  4913.6 1093.12  4974.2 1089.94  4974.9 1088.53  4976.4 1087.53
  5034.1 1088.53  5034.8 1103.24  5065.1 1112.85  5085.1  1121.6  5090.2 1121.82
  5095.5 1125.75  5125.8  1132.9  5160.4 1134.16  5216.7 1129.81    5247 1126.02
  5267.2 1119.79  5277.3 1118.98  5295.9 1122.49    5338 1122.58  5388.5 1129.17
  5436.4 1128.33  5535.6 1138.09  5576.9 1141.32  5634.7 1142.52  5875.3 1137.05
#Mann= 6 ,-1 , 0
  3967.5     .05       0  4913.6     .04       0  5034.1     .05       0
  5436.4     .12       0  5535.6     .05       0  5634.7     .12       0
Bank Sta=4974.9,5034.1
XS Rating Curve= 0 ,0
Exp/Cntr=0.3,0.1

Type RM Length L Ch R = 1 ,30612   ,1085,1085,1085
BEGIN DESCRIPTION:
Mapping XS 78208dad
END DESCRIPTION:
XS GIS Cut Line= 2
      2803567.97     10267970.65      2801784.14     10267163.37
#Sta/Elev= 30
    4378 1114.71  4490.1 1114.17  4529.2 1112.76  4742.6 1116.86  4791.2    1113
  4801.4 1111.89  4907.7 1097.04  4929.3 1092.88  4931.9 1089.85  4933.4 1088.85
  4991.1 1089.85  5054.4  1090.7  5082.5 1092.43  5132.7  1106.6  5203.2 1116.99
  5260.7 1115.55  5301.4 1119.61  5358.6 1115.74  5520.3 1137.54  5587.9 1140.69
  5641.3    1147  5730.6 1149.38  5752.6 1146.61  5785.4 1148.81  5819.5 1146.74
  5864.7  1152.9    5971 1153.89  6070.9 1150.18  6234.7 1137.96    6336 1133.03
#Mann= 13 ,-1 , 0
    4378     .05       0  4490.1     .12       0  4791.2     .05       0
  4801.4     .12       0  4907.7     .05       0  4931.9     .05       0
  4991.1     .05       0  5054.4     .12       0  5132.7     .05       0
  5203.2     .12       0  5864.7     .05       0    5971     .12       0
  6234.7     .05       0
Bank Sta=4931.9,4991.1
XS Rating Curve= 0 ,0
Exp/Cntr=0.3,0.1

Type RM Length L Ch R = 1 ,29527   ,833,833,833
BEGIN DESCRIPTION:
Mapping XS dbf264af
END DESCRIPTION:
XS GIS Cut Line= 2
      2804609.68     10266772.74       2801875.3      10266746.7
#Sta/Elev= 30
  3820.1 1132.09  3820.4 1132.09  4017.6 1124.47  4056.4 1122.47  4116.6 1120.02
  4122.2 1119.89  4514.1 1110.22  4730.4  1098.9  4744.1 1101.22  4789.1 1095.51
  4834.1 1101.08  4914.1 1101.78  4974.1  1088.5  4974.3  1086.4  4975.8  1085.4
    5034  1086.4  5104.2 1088.85  5202.7 1099.43  5301.4 1102.71  5444.2 1107.28
  5614.2 1117.42  5764.2  1132.7  5854.2 1134.99  5954.2 1130.53  6034.2  1135.7
  6084.2 1134.68  6224.2 1145.75  6387.5 1141.04  6486.3 1136.66  6554.6 1134.26
#Mann= 14 ,-1 , 0
  3820.1     .05       0  3820.4     .12       0  4017.6     .05       0
  4056.4     .12       0  4116.6     .05       0  4122.2     .12       0
  4730.4     .05       0  4789.1     .12       0  4974.3     .07       0
    5034     .12       0  5202.7     .12       0  5301.4     .05       0
  6387.5     .12       0  6486.3     .05       0
Bank Sta=4974.3,5034
XS Rating Curve= 0 ,0
Exp/Cntr=0.3,0.1

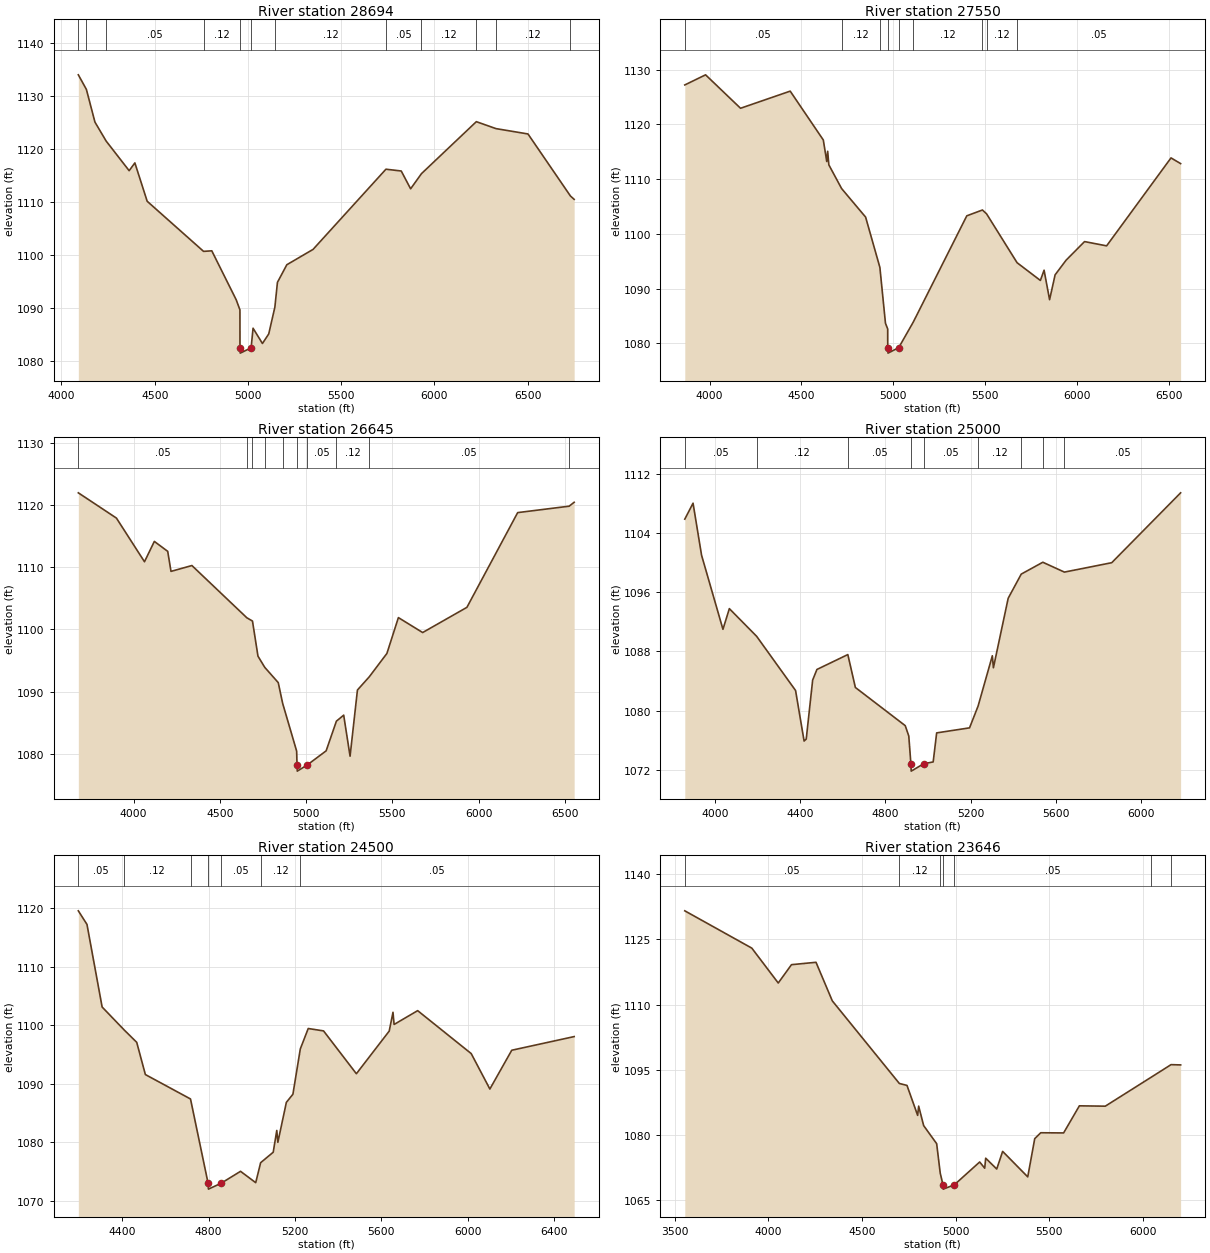
Type RM Length L Ch R = 1 ,28694   ,1144,1144,1144
BEGIN DESCRIPTION:
Mapping XS f5efd7a3
END DESCRIPTION:
XS GIS Cut Line= 2
      2804297.14     10265848.26      2801653.91     10266134.72
#Sta/Elev= 30
  4090.5 1134.04  4133.7 1131.29  4179.7 1125.11  4239.7 1121.54    4363 1115.95
  4393.7 1117.42  4459.7 1110.18  4762.1 1100.72  4806.1 1100.83  4936.9  1091.6
    4957 1089.69  4957.3 1082.52  4958.8 1081.52    5017 1082.52  5027.4 1086.22
  5077.7 1083.34  5111.5 1085.14  5144.4  1090.2  5158.2 1094.88  5208.5  1098.2
  5349.3  1101.1    5740 1116.23    5822 1115.89  5872.3 1112.53  5930.5 1115.39
  6224.7  1125.2  6329.8 1123.89  6501.6 1122.88  6729.1 1111.18  6749.2 1110.54
#Mann= 12 ,-1 , 0
  4090.5     .05       0  4133.7     .12       0  4239.7     .05       0
  4762.1     .12       0  4957.3     .05       0    5017     .12       0
  5144.4     .12       0    5740     .05       0  5930.5     .12       0
  6224.7     .05       0  6329.8     .12       0  6729.1     .05       0
Bank Sta=4957.3,5017
XS Rating Curve= 0 ,0
Exp/Cntr=0.3,0.1

Type RM Length L Ch R = 1 ,27550   ,905,905,905
BEGIN DESCRIPTION:
Mapping XS cf0e7c4c
END DESCRIPTION:
XS GIS Cut Line= 2
       2804648.7      10264936.8      2801953.41     10264767.53
#Sta/Elev= 30
  3865.1 1127.21  3978.3 1129.06  4168.7 1122.95  4439.2 1126.08  4619.6 1117.15
  4638.3 1113.22  4643.3 1115.09  4649.7 1112.61  4719.2 1108.28    4850 1103.06
  4927.7 1093.87  4958.1 1083.66  4970.3 1082.62  4970.4 1079.21  4971.9 1078.21
  5030.2 1079.21  5109.8  1083.9  5401.1  1103.3  5486.2 1104.36  5508.6 1103.67
    5675 1094.73  5801.9 1091.49    5822 1093.36    5852 1087.97  5882.1 1092.52
  5942.2  1095.2  6042.4 1098.59  6162.6 1097.81  6513.3 1113.88  6565.7 1112.84
#Mann= 9 ,-1 , 0
  3865.1     .05       0  4719.2     .12       0  4927.7     .05       0
  4970.4     .05       0  5030.2     .05       0  5109.8     .12       0
  5486.2     .05       0  5508.6     .12       0    5675     .05       0
Bank Sta=4970.4,5030.2
XS Rating Curve= 0 ,0
Exp/Cntr=0.3,0.1

Type RM Length L Ch R = 1 ,26645   ,1645,1645,1645
BEGIN DESCRIPTION:
Mapping XS 919089ee
END DESCRIPTION:
XS GIS Cut Line= 3
      2804609.64     10264650.32      2804284.14     10264272.74
      2802059.09     10263439.97
#Sta/Elev= 30
  3679.9 1121.96  3900.7  1117.9  4063.4 1110.88  4120.5 1114.15  4198.1 1112.55
  4217.1 1109.33  4338.3 1110.27  4656.9 1101.87  4689.4 1101.35  4721.3  1095.7
  4760.7  1093.9  4838.8 1091.45  4864.5  1088.1  4945.5 1080.44  4947.7 1078.22
  4949.2 1077.22  5007.5 1078.22  5116.4 1080.48  5175.9 1085.25  5218.2 1086.22
  5255.2 1079.62  5297.9 1090.26  5366.7 1092.39  5468.7 1096.14  5535.3  1101.9
    5676  1099.5  5932.5 1103.55  6226.8 1118.78    6525 1119.81  6554.2 1120.44
#Mann= 10 ,-1 , 0
  3679.9     .05       0  4656.9     .12       0  4689.4     .05       0
  4760.7     .12       0  4864.5     .05       0  4947.7     .03       0
  5007.5     .05       0  5175.9     .12       0  5366.7     .05       0
    6525     .12       0
Bank Sta=4947.7,5007.5
XS Rating Curve= 0 ,0
Exp/Cntr=0.3,0.1

Type RM Length L Ch R = 1 ,25000   ,500,500,500
BEGIN DESCRIPTION:
PECAN CREEK 50.0
END DESCRIPTION:
XS GIS Cut Line= 3
      2804974.28     10262501.91      2803835.38     10262564.03
      2802670.16     10262775.24
#Sta/Elev= 30
  3859.4 1105.86  3898.1 1108.01  3938.1 1100.98  4038.3 1090.99  4068.3 1093.78
  4196.4 1090.04  4378.8 1082.73  4418.8 1075.91  4428.8 1076.18  4458.9 1084.14
  4478.9 1085.57  4623.8 1087.58  4659.2 1083.14  4892.9 1077.99  4909.6 1076.59
  4919.5 1072.85    4921 1071.85  4979.7 1072.85    5024 1073.09  5040.3 1077.01
  5194.5 1077.69  5234.6 1080.63  5301.4 1087.42  5306.4  1085.8  5375.7 1095.18
  5436.9 1098.44  5538.1 1100.04  5639.3 1098.71  5861.2 1099.98  6184.2 1109.41
#Mann= 9 ,-1 , 0
  3859.4     .05       0  4196.4     .12       0  4623.8     .05       0
  4919.5     .05       0  4979.7     .05       0  5234.6     .12       0
  5436.9     .05       0  5538.1     .12       0  5639.3     .05       0
Bank Sta=4919.5,4979.7
XS Rating Curve= 0 ,0
Exp/Cntr=0.3,0.1

Type RM Length L Ch R = 1 ,24500   ,854,854,854
BEGIN DESCRIPTION:
PECAN CREEK 49.0
END DESCRIPTION:
XS GIS Cut Line= 3
      2804905.68     10262203.11      2804103.43     10262148.64
      2802630.55     10262397.73
#Sta/Elev= 30
  4195.9 1119.52    4236  1117.2  4306.2  1103.1  4408.2 1099.19  4466.5 1097.07
  4506.6 1091.57  4715.8  1087.4  4797.3 1073.01  4798.8 1072.01  4857.5 1073.01
  4947.6 1075.05    5018 1073.11  5040.8 1076.52  5099.1 1078.31  5115.6 1082.03
  5120.6    1080    5160 1086.82  5190.4 1088.21  5224.7 1095.95  5261.4 1099.43
  5332.4 1099.02  5484.5 1091.71  5636.7 1098.99  5654.2  1102.2  5659.3 1100.12
  5768.5 1102.48  6016.7 1095.15  6103.2  1089.1  6204.6 1095.72  6493.8 1098.05
#Mann= 7 ,-1 , 0
  4195.9     .05       0  4408.2     .12       0  4715.8     .05       0
  4797.3     .05       0  4857.5     .05       0  5040.8     .12       0
  5224.7     .05       0
Bank Sta=4797.3,4857.5
XS Rating Curve= 0 ,0
Exp/Cntr=0.3,0.1

Type RM Length L Ch R = 1 ,23646   ,478,478,478
BEGIN DESCRIPTION:
PECAN CREEK 48.0
END DESCRIPTION:
XS GIS Cut Line= 4
      2805680.66     10261578.11      2804454.81     10261421.45
      2803594.24     10261144.29      2803136.32     10260925.31
#Sta/Elev= 30
  3553.3  1131.6  3911.2 1123.01  4052.3 1114.98  4122.9  1119.2  4253.9 1119.75
  4340.9 1110.87  4698.9 1091.85  4739.7  1091.4  4796.7  1084.5    4802 1086.63
  4828.8 1082.14  4898.2 1077.98  4917.2 1071.21  4931.9 1068.52  4933.4 1067.52
  4992.7 1068.52  5127.9 1073.77  5154.7 1072.34    5160 1074.64  5218.9 1072.15
  5250.5 1076.21  5384.5 1070.34  5421.8 1079.14  5453.9  1080.5  5576.1 1080.46
  5660.2  1086.7  5798.6 1086.62  6042.3 1093.25  6149.6 1096.18  6200.8 1096.12
#Mann= 7 ,-1 , 0
  3553.3     .05       0  4698.9     .12       0  4917.2     .05       0
  4931.9     .05       0  4992.7     .05       0  6042.3     .12       0
  6149.6     .05       0
Bank Sta=4931.9,4992.7
XS Rating Curve= 0 ,0
Exp/Cntr=0.3,0.1

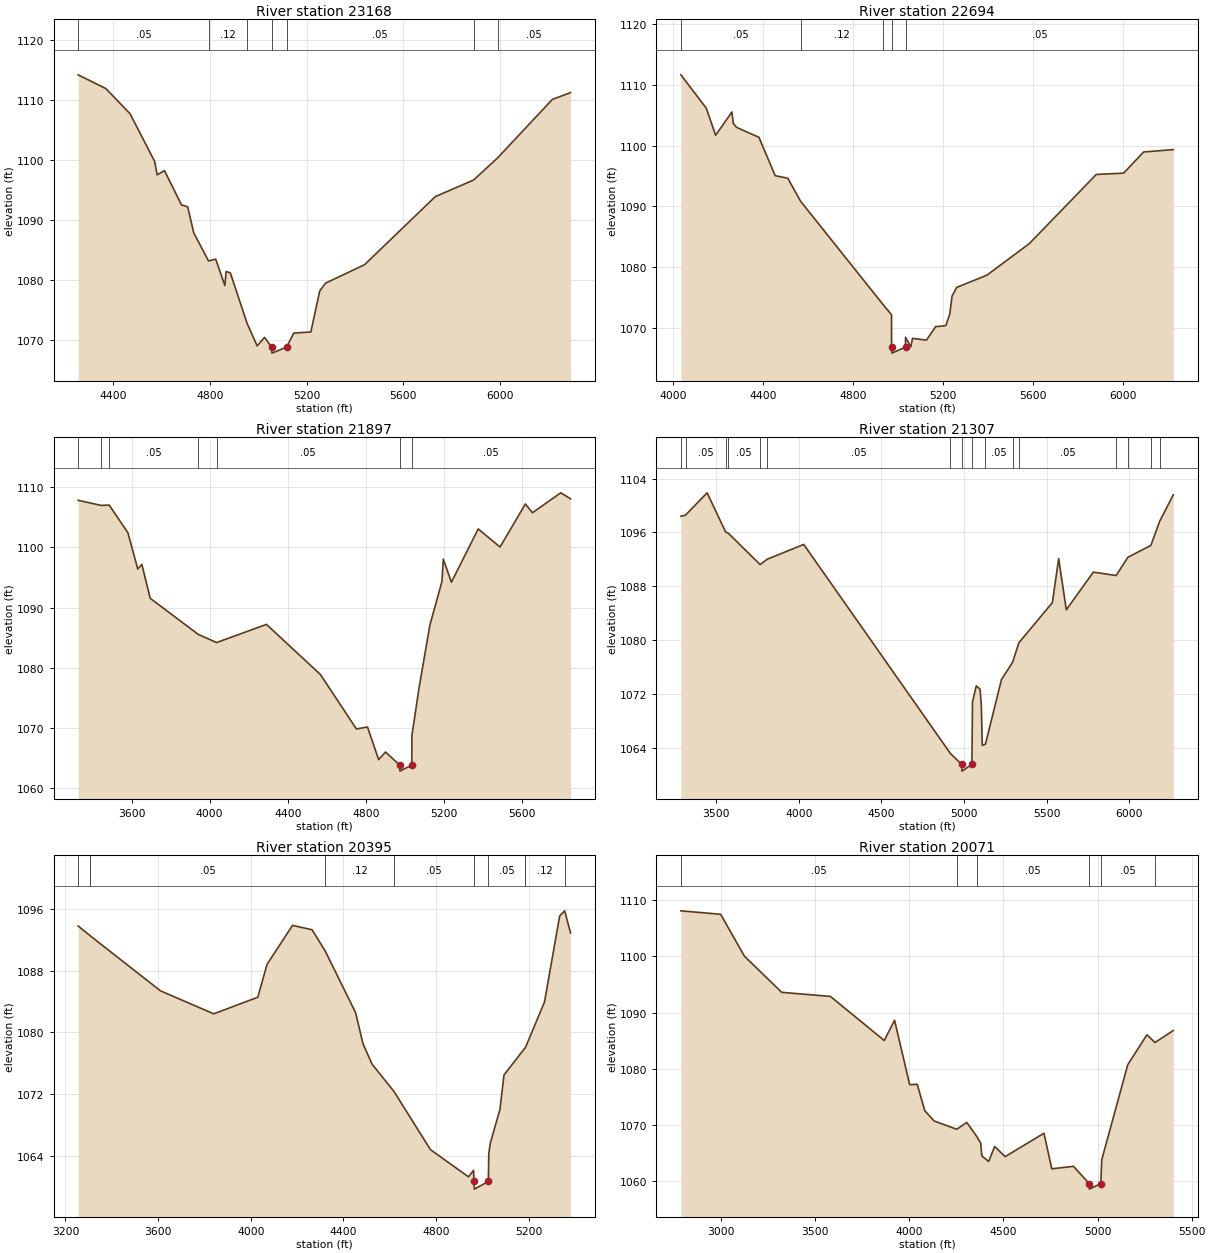
Type RM Length L Ch R = 1 ,23168   ,474,474,474
BEGIN DESCRIPTION:
Mapping XS f365a789
END DESCRIPTION:
XS GIS Cut Line= 2
       2804909.4     10260986.04      2802891.14     10260725.62
#Sta/Elev= 30
  4256.2  1114.2  4370.9  1111.9  4470.5 1107.72  4572.5 1099.74  4582.6 1097.51
  4612.9 1098.22  4683.4 1092.49  4708.8 1092.18  4733.8 1087.85  4795.1 1083.14
  4824.6 1083.45  4862.5 1079.05  4867.6  1081.4  4885.1 1081.15  4954.3 1072.75
    4996 1068.98  5026.4  1070.4  5055.8 1068.77  5057.3 1067.77  5117.7 1068.77
  5147.2 1071.11  5217.8  1071.3  5254.5 1078.13  5278.3 1079.44  5439.7 1082.52
  5732.1 1093.88  5890.4 1096.65  5989.4 1100.33    6216  1110.1  6291.2 1111.24
#Mann= 7 ,-1 , 0
  4256.2     .05       0  4795.1     .12       0  4954.3     .05       0
  5055.8     .05       0  5117.7     .05       0  5890.4     .12       0
  5989.4     .05       0
Bank Sta=5055.8,5117.7
XS Rating Curve= 0 ,0
Exp/Cntr=0.3,0.1

Type RM Length L Ch R = 1 ,22694   ,797,797,797
BEGIN DESCRIPTION:
Mapping XS 1d5cccaf
END DESCRIPTION:
XS GIS Cut Line= 4
      2804935.43     10260920.94      2804388.55     10260491.25
      2803750.53     10260321.97      2802995.34     10259970.42
#Sta/Elev= 30
  4034.7 1111.66  4147.5 1106.18  4189.1 1101.71  4261.4 1105.54  4267.8 1103.67
  4282.2 1103.01  4381.6 1101.38  4453.9 1095.06    4510 1094.64  4566.6 1090.86
  4933.3 1073.85  4971.1 1072.16  4971.2 1066.85  4972.7 1065.85  5033.1 1066.85
  5033.2 1068.46  5056.7 1066.89  5064.2 1068.28  5126.3 1067.99  5166.9  1070.2
  5212.3 1070.38  5229.8  1072.3  5240.1 1075.24  5260.8 1076.67  5394.9 1078.68
  5583.2 1083.87    5881 1095.26  6002.3 1095.47  6091.3 1098.96  6223.3 1099.35
#Mann= 5 ,-1 , 0
  4034.7     .05       0  4566.6     .12       0  4933.3     .05       0
  4971.2     .05       0  5033.1     .05       0
Bank Sta=4971.2,5033.1
XS Rating Curve= 0 ,0
Exp/Cntr=0.3,0.1

Type RM Length L Ch R = 1 ,21897   ,590,590,590
BEGIN DESCRIPTION:
Mapping XS 5f620647
END DESCRIPTION:
XS GIS Cut Line= 3
      2805326.06     10260712.61      2804167.19     10259696.97
       2803216.7     10259462.61
#Sta/Elev= 30
    3327 1107.84  3444.4    1107  3485.8 1107.05  3581.7 1102.44    3632 1096.41
  3652.9 1097.19  3695.6 1091.54  3941.3 1085.54  4035.5 1084.17  4290.6 1087.19
  4566.8 1078.85  4750.9 1069.79  4807.8 1070.11  4864.8 1064.68  4900.1 1065.95
  4972.4 1063.77  4973.9 1062.77  5034.3 1063.77  5034.9 1068.67  5071.2 1076.57
    5127 1087.08  5188.8 1094.35  5195.6 1098.06  5237.1 1094.21  5374.2 1103.08
    5486 1100.07  5615.6 1107.23    5652 1105.78  5796.4 1109.09  5846.9  1108.1
#Mann= 7 ,-1 , 0
    3327     .05       0  3444.4     .12       0  3485.8     .05       0
  3941.3     .12       0  4035.5     .05       0  4972.4     .05       0
  5034.3     .05       0
Bank Sta=4972.4,5034.3
XS Rating Curve= 0 ,0
Exp/Cntr=0.3,0.1

Type RM Length L Ch R = 1 ,21307   ,912,912,912
BEGIN DESCRIPTION:
Mapping XS d0c1e8ad
END DESCRIPTION:
XS GIS Cut Line= 5
      2805300.03     10260491.26      2804948.44     10260230.83
      2804622.92     10259723.02      2804219.28     10259006.87
      2803816.18     10257966.63
#Sta/Elev= 30
    3287 1098.39  3315.4 1098.58  3445.7 1101.88    3558 1096.05  3572.9  1095.9
  3766.4 1091.22  3809.6 1092.02  4030.1 1094.21  4917.1 1063.16  4985.4 1061.53
  4986.9 1060.53  5047.3 1061.53  5050.8 1070.81  5073.8  1073.2  5096.7 1072.71
  5104.3 1070.34  5110.1 1064.36  5129.3 1064.54  5226.2 1074.14  5293.2 1076.69
  5331.4  1079.6    5534 1085.57  5572.1 1092.11  5618.4  1084.5  5781.8  1090.1
  5919.6 1089.59  5990.6  1092.3    6130 1094.07  6182.9 1097.65  6265.4 1101.58
#Mann= 16 ,-1 , 0
    3287     .12       0  3315.4     .05       0    3558     .12       0
  3572.9     .05       0  3766.4     .12       0  3809.6     .05       0
  4917.1     .12       0  4985.4     .07       0  5047.3     .12       0
  5129.3     .05       0  5293.2     .12       0  5331.4     .05       0
  5919.6     .12       0  5990.6     .05       0    6130     .12       0
  6182.9     .05       0
Bank Sta=4985.4,5047.3
XS Rating Curve= 0 ,0
Exp/Cntr=0.3,0.1

Type RM Length L Ch R = 1 ,20395   ,324,324,324
BEGIN DESCRIPTION:
Mapping XS 94453e2b
END DESCRIPTION:
XS GIS Cut Line= 4
      2805028.87     10260198.52      2805028.87     10259249.23
       2804937.7     10258594.93      2804787.52     10258101.49
#Sta/Elev= 30
  3254.8 1093.84  3306.2 1092.59  3307.1 1092.56  3610.2 1085.41  3840.2 1082.42
  4030.2 1084.58  4070.2 1088.85  4180.2 1093.92  4264.6 1093.35  4321.1  1090.6
  4452.6 1082.57  4484.4 1078.53  4523.3  1075.9  4618.5 1072.32  4775.7 1064.77
  4939.8 1061.24  4961.7 1062.08  4963.6 1060.64  4965.1 1059.64  5025.6 1060.64
  5027.4 1064.22  5033.9 1065.61  5075.7    1070  5093.1 1074.48  5182.8 1077.95
  5184.9 1077.99  5267.8 1083.95  5333.5 1095.14    5355 1095.81  5380.5 1092.94
#Mann= 10 ,-1 , 0
  3254.8     .05       0  3306.2     .12       0  3307.1     .05       0
  4321.1     .12       0  4618.5     .05       0  4963.6     .03       0
  5025.6     .05       0  5182.8     .05       0  5184.9     .12       0
    5355     .05       0
Bank Sta=4963.6,5025.6
XS Rating Curve= 0 ,0
Exp/Cntr=0.3,0.1

Type RM Length L Ch R = 1 ,20071   ,571,571,571
BEGIN DESCRIPTION:
Mapping XS d7c30645
END DESCRIPTION:
XS GIS Cut Line= 6
      2805742.16     10260396.91      2805533.01     10259694.37
        2805592.     10258954.26       2805490.1     10258664.65
      2805313.12     10258519.84      2804976.04     10258016.91
#Sta/Elev= 30
  2785.8 1108.14  2997.2 1107.52  3123.6 1100.05  3321.9 1093.61  3580.3 1092.89
  3866.6 1085.03  3921.3 1088.64  4001.6 1077.16  4041.7 1077.22  4081.8 1072.52
    4132 1070.68  4251.9 1069.21  4304.9 1070.43  4356.9 1067.98  4379.1 1066.73
  4385.1 1064.46  4421.5 1063.47  4453.3 1066.14  4508.9 1064.33  4715.2  1068.5
  4756.8 1062.16  4872.2  1062.6  4955.3 1059.54  4956.8 1058.54  5017.3 1059.54
  5022.3 1063.78  5160.4 1080.71  5262.4 1086.05  5305.1 1084.67  5402.4 1086.81
#Mann= 6 ,-1 , 0
  2785.8     .05       0  4251.9     .12       0  4356.9     .05       0
  4955.3     .07       0  5017.3     .05       0  5305.1     .05       0
Bank Sta=4955.3,5017.3
XS Rating Curve= 0 ,0
Exp/Cntr=0.3,0.1

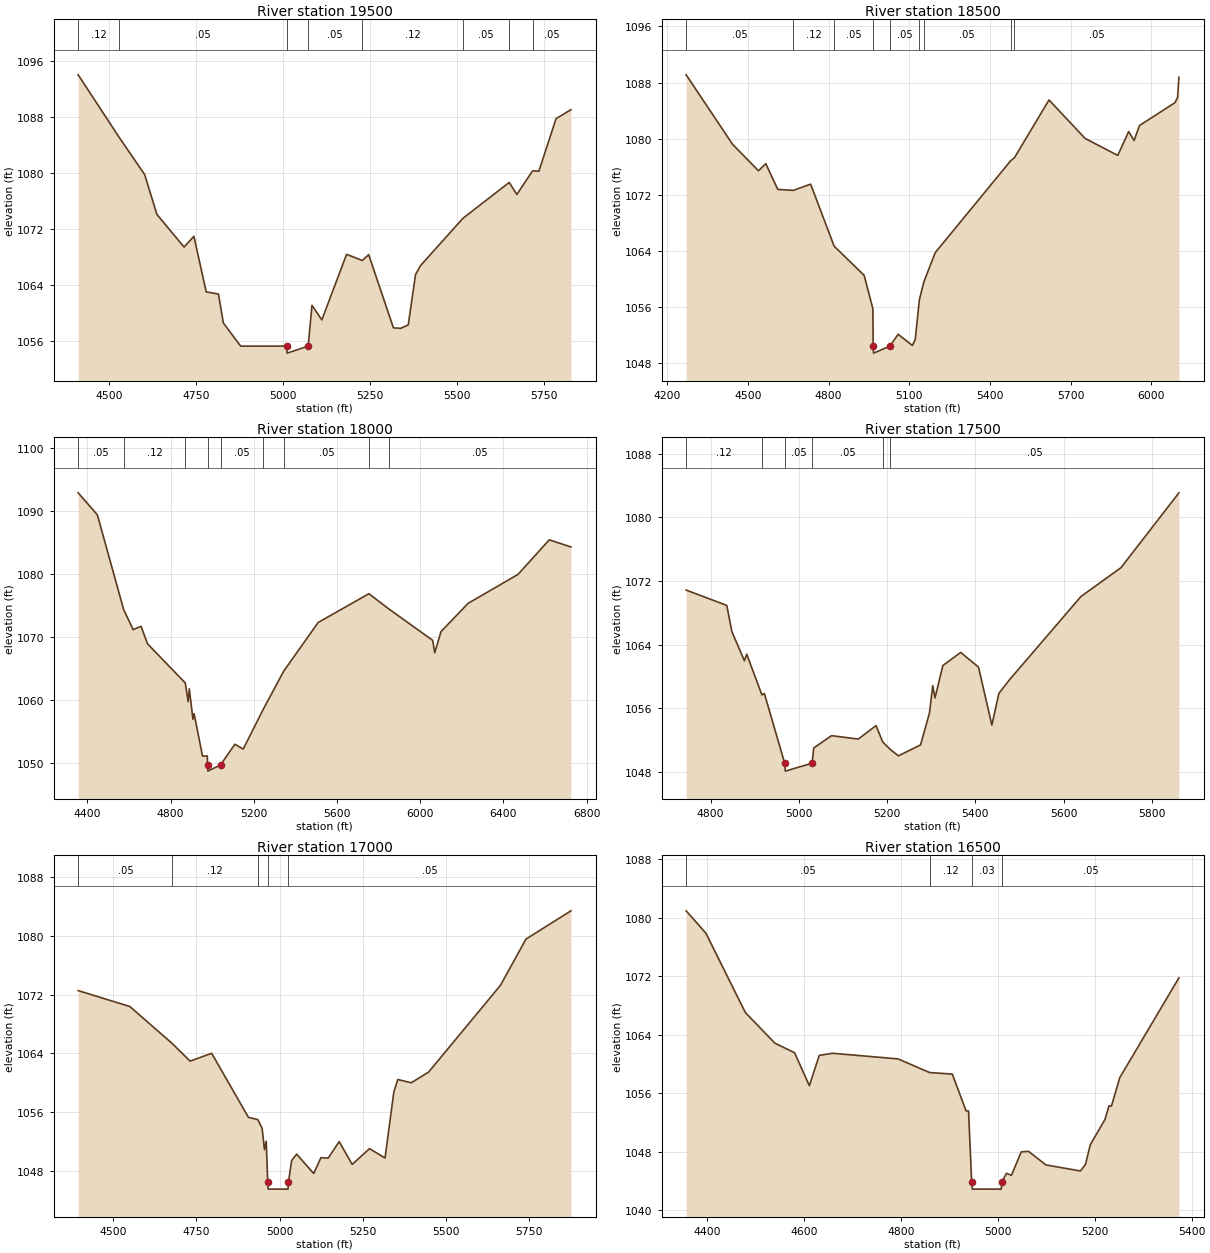
Type RM Length L Ch R = 1 ,19500   ,1000,1000,1000
BEGIN DESCRIPTION:
PECAN CREEK 39.0
END DESCRIPTION:
XS GIS Cut Line= 3
      2806155.67     10258903.09      2805747.62       10258480.
      2805130.66     10257928.09
#Sta/Elev= 30
  4412.2 1094.01  4529.5 1085.11  4603.2 1079.76  4638.4 1074.06  4716.4  1069.4
  4744.7 1070.94  4779.9    1063  4815.2 1062.68  4829.3 1058.55    4879 1055.24
  5010.9 1055.24  5012.4 1054.24    5073 1055.24  5083.8 1061.07  5112.2 1058.99
  5183.3 1068.36  5228.5 1067.48  5246.8 1068.31  5317.9 1057.85  5338.8 1057.78
  5360.5 1058.28  5381.4 1065.47  5395.6 1066.74  5517.6 1073.51  5650.5 1078.63
  5672.3 1076.91  5717.6 1080.28  5735.8 1080.25  5785.1 1087.75  5827.8 1089.03
#Mann= 8 ,-1 , 0
  4412.2     .12       0  4529.5     .05       0  5010.9     .05       0
    5073     .05       0  5228.5     .12       0  5517.6     .05       0
  5650.5     .12       0  5717.6     .05       0
Bank Sta=5010.9,5073
XS Rating Curve= 0 ,0
Exp/Cntr=0.3,0.1

Type RM Length L Ch R = 1 ,18500   ,500,500,500
BEGIN DESCRIPTION:
PECAN CREEK 37.0
END DESCRIPTION:
XS GIS Cut Line= 4
      2806630.68      10258478.1      2806410.72     10257781.82
      2806186.22     10257702.38      2805330.65     10257828.12
#Sta/Elev= 30
  4269.8  1089.1  4442.8 1079.19  4538.9 1075.43    4566 1076.45  4610.6 1072.78
  4668.1 1072.64  4732.9 1073.53  4820.2  1064.7  4932.1 1060.53  4964.4 1055.78
  4965.6 1050.46  4967.1 1049.46  5027.7 1050.46  5058.4 1052.15  5111.4 1050.55
    5122 1051.41  5137.3 1057.03  5154.1 1059.61  5196.3 1063.77  5477.2 1076.87
    5491 1077.29  5619.6 1085.52    5754 1080.04  5875.4 1077.62  5915.9 1081.02
  5936.1 1079.75  5956.3 1081.88  6087.7 1085.12  6097.8 1085.85  6102.9 1088.76
#Mann= 9 ,-1 , 0
  4269.8     .05       0  4668.1     .12       0  4820.2     .05       0
  4965.6     .05       0  5027.7     .05       0  5137.3     .12       0
  5154.1     .05       0  5477.2     .12       0    5491     .05       0
Bank Sta=4965.6,5027.7
XS Rating Curve= 0 ,0
Exp/Cntr=0.3,0.1

Type RM Length L Ch R = 1 ,18000   ,500,500,500
BEGIN DESCRIPTION:
PECAN CREEK 36.0
END DESCRIPTION:
XS GIS Cut Line= 3
      2807230.73     10257078.09      2806644.25     10257345.82
      2804921.56      10257420.4
#Sta/Elev= 30
  4355.3 1092.93  4447.5 1089.43  4573.8 1074.37  4619.7 1071.16  4657.6 1071.69
  4688.8  1068.9  4870.1 1062.68  4884.1  1059.7  4889.6 1061.76  4907.1 1056.91
  4912.6 1057.79  4953.2 1051.03  4976.2 1051.06  4977.4 1049.65  4978.9 1048.65
  5039.8 1049.65  5108.7 1052.93  5148.7 1052.16  5244.6 1058.45  5343.7 1064.57
    5509  1072.3    5753 1076.88  5849.9 1074.43  6059.6 1069.46  6069.6 1067.49
  6099.6 1070.85  6229.7 1075.34  6469.9 1079.95  6620.1 1085.45  6724.3 1084.32
#Mann= 9 ,-1 , 0
  4355.3     .05       0  4573.8     .12       0  4870.1     .05       0
  4977.4     .05       0  5039.8     .05       0  5244.6     .12       0
  5343.7     .05       0    5753     .12       0  5849.9     .05       0
Bank Sta=4977.4,5039.8
XS Rating Curve= 0 ,0
Exp/Cntr=0.3,0.1

Type RM Length L Ch R = 1 ,17500   ,500,500,500
BEGIN DESCRIPTION:
PECAN CREEK 35.0
END DESCRIPTION:
XS GIS Cut Line= 3
      2806955.64     10256803.12       2806709.2     10256869.44
       2805855.7     10256753.11
#Sta/Elev= 30
  4744.8 1070.87  4836.9 1068.94  4848.3 1065.66  4876.8 1061.98    4882 1062.81
  4916.5 1057.68    4922 1057.87    4968  1049.1  4969.5  1048.1  5030.4  1049.1
  5033.8 1051.01  5074.2 1052.56  5134.8 1052.13  5175.1 1053.83  5190.1 1051.77
  5206.6 1050.87  5225.6 1050.02    5276  1051.4  5296.2 1055.43  5303.6 1058.85
  5308.7 1057.31  5326.5 1061.38  5366.9 1063.03  5407.3 1061.18  5437.5 1053.89
  5453.4 1057.87  5477.9 1059.62  5639.4 1070.06  5730.2 1073.69  5861.4  1083.1
#Mann= 6 ,-1 , 0
  4744.8     .12       0  4916.5     .05       0    4968     .05       0
  5030.4     .05       0  5190.1     .12       0  5206.6     .05       0
Bank Sta=4968,5030.4
XS Rating Curve= 0 ,0
Exp/Cntr=0.3,0.1

Type RM Length L Ch R = 1 ,17000   ,500,500,500
BEGIN DESCRIPTION:
PECAN CREEK 34.0
END DESCRIPTION:
XS GIS Cut Line= 3
      2807141.93      10256546.2      2806555.08     10256397.46
      2805715.39      10256648.1
#Sta/Elev= 30
  4394.6 1072.54  4550.1 1070.37  4678.2 1065.31  4731.2 1062.94    4796 1064.01
  4906.5  1055.3  4934.8 1054.99  4947.8 1053.79  4954.8  1050.9    4960 1052.04
  4964.6 1046.53  4966.1 1045.53  5025.5 1045.53    5027 1046.53  5036.6 1049.44
  5051.6 1050.29  5102.8 1047.65  5124.6 1049.81  5146.4 1049.75  5179.5    1052
  5218.5 1048.89  5270.7 1051.04  5317.3 1049.76  5343.8 1058.75  5355.7 1060.44
  5395.9    1060  5448.1 1061.44  5664.3 1073.25    5741 1079.54  5876.3 1083.39
#Mann= 5 ,-1 , 0
  4394.6     .05       0  4678.2     .12       0  4934.8     .05       0
  4964.6     .05       0    5027     .05       0
Bank Sta=4964.6,5027
XS Rating Curve= 0 ,0
Exp/Cntr=0.3,0.1

Type RM Length L Ch R = 1 ,16500   ,500,500,500
BEGIN DESCRIPTION:
PECAN CREEK 33.0
END DESCRIPTION:
XS GIS Cut Line= 3
      2807055.72      10255803.1      2806423.52     10255919.36
      2806055.64      10255853.1
#Sta/Elev= 30
  4357.2 1080.94  4397.9 1077.89  4479.3 1067.04  4540.3 1062.85  4580.9 1061.54
  4611.4 1057.04  4631.8 1061.18  4659.3 1061.47  4794.4  1060.7  4859.3 1058.84
  4906.3 1058.62  4934.8 1053.58  4939.8 1053.58  4946.2  1043.9  4947.7  1042.9
  5007.2  1042.9  5008.7  1043.9  5018.1 1045.06  5028.3 1044.79  5048.6    1048
  5063.6 1048.06  5099.4 1046.21  5170.5 1045.38    5181 1046.27  5190.9 1048.96
  5221.3 1052.43  5229.6  1054.3  5234.6 1054.26  5251.8 1058.14  5373.8 1071.78
#Mann= 4 ,-1 , 0
  4357.2     .05       0  4859.3     .12       0  4946.2     .03       0
  5008.7     .05       0
Bank Sta=4946.2,5008.7
XS Rating Curve= 0 ,0
Exp/Cntr=0.3,0.1

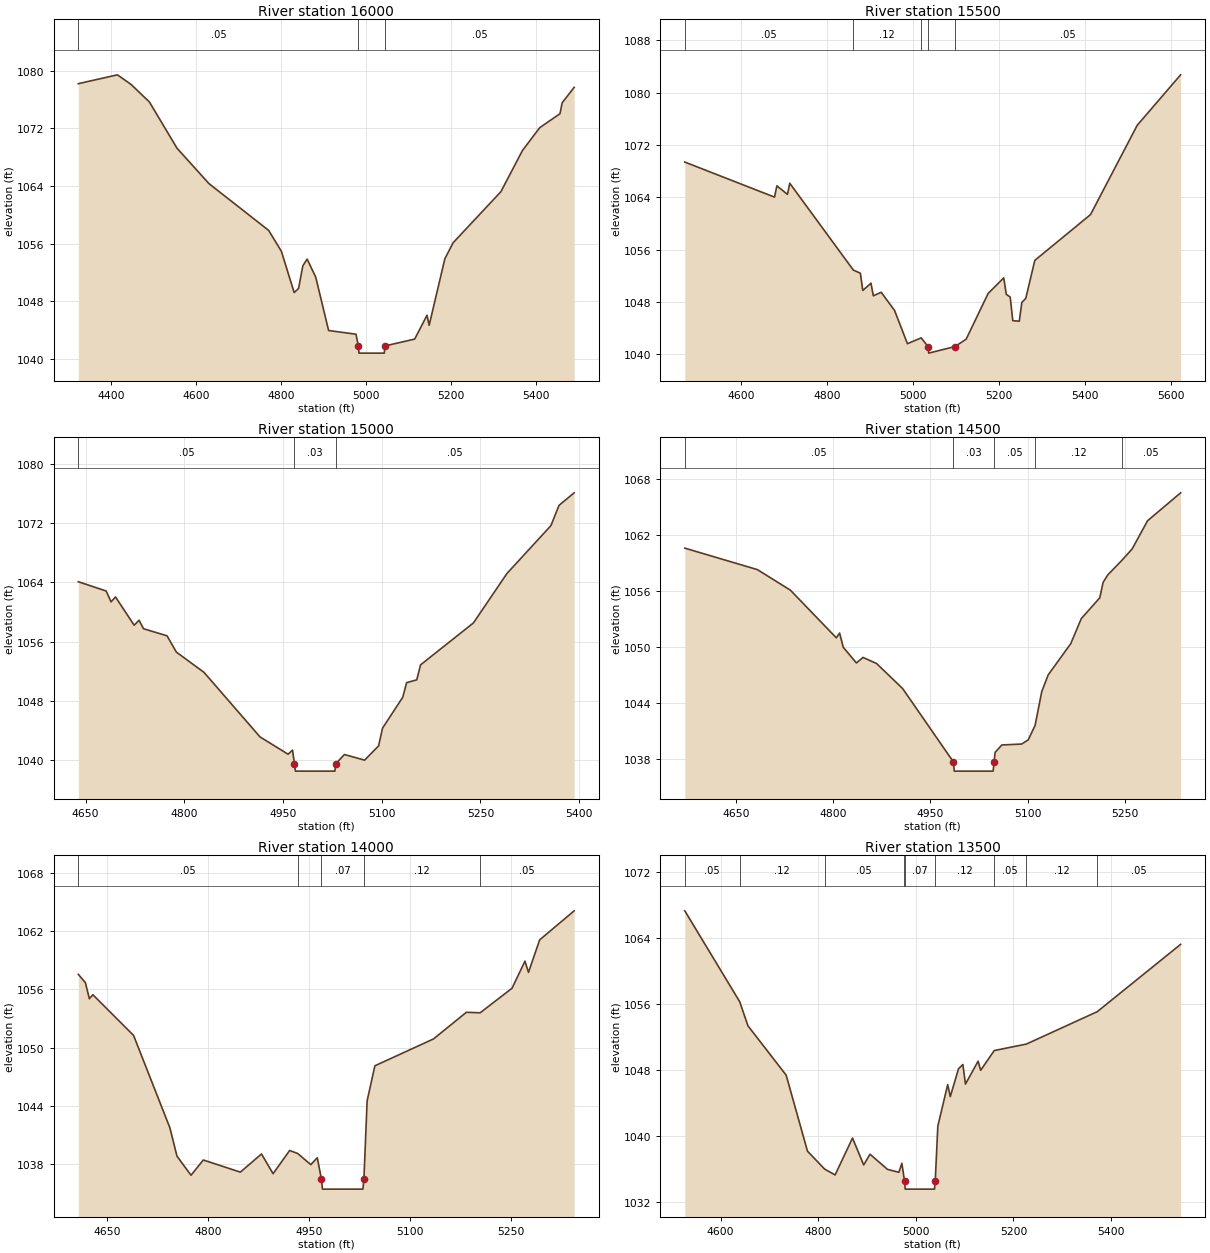
Type RM Length L Ch R = 1 ,16000   ,500,500,500
BEGIN DESCRIPTION:
PECAN CREEK 32.0
END DESCRIPTION:
XS GIS Cut Line= 3
      2807158.09     10255521.85      2806488.73     10255424.52
      2806005.68     10255503.11
#Sta/Elev= 30
  4323.6 1078.21  4415.5 1079.44  4447.3 1078.12  4490.7 1075.67  4555.7 1069.24
  4630.9 1064.32  4771.1 1057.83    4801 1054.93  4831.1 1049.19  4841.4 1049.76
  4851.5 1052.91  4861.6 1053.84  4881.8 1051.33  4912.1 1043.92  4976.4 1043.41
    4982 1041.78  4983.5 1040.78    5043 1040.78  5044.5 1041.78  5114.5 1042.73
  5143.4 1046.04  5148.5 1044.65  5185.4 1053.89  5204.9 1056.12  5317.2 1063.21
  5367.8 1068.92  5408.3 1072.09  5456.1 1074.04  5461.2 1075.56  5489.4  1077.7
#Mann= 3 ,-1 , 0
  4323.6     .05       0    4982     .03       0  5044.5     .05       0
Bank Sta=4982,5044.5
XS Rating Curve= 0 ,0
Exp/Cntr=0.3,0.1

Type RM Length L Ch R = 1 ,15500   ,500,500,500
BEGIN DESCRIPTION:
PECAN CREEK 31.0
END DESCRIPTION:
XS GIS Cut Line= 3
      2807222.44     10255183.98      2806726.86      10254994.4
      2806205.67      10254653.1
#Sta/Elev= 30
  4469.4 1069.39  4678.2 1064.03  4683.6 1065.76  4708.3 1064.45  4713.6 1066.15
  4861.6 1052.88  4877.9  1052.4  4883.5 1049.77  4902.6 1050.88    4908 1048.95
  4926.3 1049.49  4957.4 1046.72  4987.4 1041.63  5019.4 1042.52  5035.4 1041.19
  5036.9 1040.19  5097.9 1041.19    5124 1042.32  5175.2 1049.31  5211.4 1051.69
  5217.4 1049.18  5226.5 1048.76  5232.5 1045.15  5247.6 1045.07  5253.6 1047.94
  5262.7 1048.56  5283.8 1054.37  5413.4 1061.36    5522 1075.01    5623 1082.72
#Mann= 5 ,-1 , 0
  4469.4     .05       0  4861.6     .12       0  5019.4     .05       0
  5035.4     .07       0  5097.9     .05       0
Bank Sta=5035.4,5097.9
XS Rating Curve= 0 ,0
Exp/Cntr=0.3,0.1

Type RM Length L Ch R = 1 ,15000   ,500,500,500
BEGIN DESCRIPTION:
PECAN CREEK 30.0
END DESCRIPTION:
XS GIS Cut Line= 3
      2807155.71     10254803.14      2806912.58     10254536.42
      2806705.68     10254203.11
#Sta/Elev= 30
  4639.1 1064.07  4681.4 1062.82  4688.8 1061.36  4695.6 1062.02  4723.9 1058.21
  4731.4 1058.88  4738.1 1057.74  4773.9 1056.78    4788 1054.59    4830 1051.86
  4915.1 1043.16  4957.7 1040.83  4964.5 1041.38  4967.4 1039.55  4968.9 1038.55
  5028.8 1038.55  5030.3 1039.55  5043.3 1040.79    5074 1040.03  5095.3 1041.96
  5101.2 1044.34  5131.9  1048.5  5137.8 1050.47  5153.2 1050.85    5159 1052.87
  5239.3 1058.52  5290.1 1065.17    5357 1071.63  5369.3 1074.36  5392.3 1076.05
#Mann= 3 ,-1 , 0
  4639.1     .05       0  4967.4     .03       0  5030.3     .05       0
Bank Sta=4967.4,5030.3
XS Rating Curve= 0 ,0
Exp/Cntr=0.3,0.1

Type RM Length L Ch R = 1 ,14500   ,500,500,500
BEGIN DESCRIPTION:
PECAN CREEK 29.0
END DESCRIPTION:
XS GIS Cut Line= 3
      2807355.68     10254653.07      2807274.72     10254232.08
      2807205.69     10253903.15
#Sta/Elev= 30
  4571.3 1060.61  4683.3 1058.31  4734.2 1056.11    4805 1051.01  4810.1 1051.52
  4815.7    1050    4836 1048.32  4846.2 1048.91  4867.1 1048.26  4907.3 1045.58
  4985.5 1037.74    4987 1036.74  5046.9 1036.74  5048.4 1037.74    5050 1038.75
  5060.3 1039.54  5090.9 1039.64  5101.1 1040.09  5111.6 1041.63  5121.9 1045.25
  5131.8 1047.04  5166.6 1050.38  5182.9 1053.07  5211.4 1055.29  5216.5 1056.94
  5223.7 1057.74  5245.3 1059.29  5261.3 1060.52  5285.1 1063.54  5336.1 1066.53
#Mann= 5 ,-1 , 0
  4571.3     .05       0  4985.5     .03       0  5048.4     .05       0
  5111.6     .12       0  5245.3     .05       0
Bank Sta=4985.5,5048.4
XS Rating Curve= 0 ,0
Exp/Cntr=0.3,0.1

Type RM Length L Ch R = 1 ,14000   ,500,500,500
BEGIN DESCRIPTION:
PECAN CREEK 28.0
END DESCRIPTION:
XS GIS Cut Line= 3
      2807705.69     10254253.11      2807590.83     10253877.59
       2807255.7     10253803.12
#Sta/Elev= 30
  4607.3 1057.56  4617.8  1056.7  4623.7 1055.05  4628.9 1055.46  4689.3 1051.27
  4743.2 1041.76  4753.7 1038.84  4774.6 1036.87  4792.8 1038.44  4847.8 1037.19
  4879.2 1039.06  4896.4 1037.03    4921 1039.42  4932.9 1039.11  4952.4 1037.96
    4962 1038.67  4968.2 1036.44  4969.7 1035.44  5029.7 1035.44  5031.2 1036.44
    5036 1044.54  5047.5 1048.14  5134.6 1050.91  5183.3 1053.65  5203.8  1053.6
  5251.1 1056.13  5270.3 1058.92  5275.5 1057.76  5292.1 1061.11  5343.3  1064.1
#Mann= 5 ,-1 , 0
  4607.3     .05       0  4932.9     .12       0  4968.2     .07       0
  5031.2     .12       0  5203.8     .05       0
Bank Sta=4968.2,5031.2
XS Rating Curve= 0 ,0
Exp/Cntr=0.3,0.1

Type RM Length L Ch R = 1 ,13500   ,451,451,451
BEGIN DESCRIPTION:
PECAN CREEK 27.0
END DESCRIPTION:
XS GIS Cut Line= 3
      2808205.66     10253903.08      2807933.47     10253515.64
      2807755.68      10253003.1
#Sta/Elev= 30
  4526.5 1067.26    4639 1056.25  4655.9 1053.33  4734.2 1047.35  4777.9 1038.14
    4813 1035.97  4834.5 1035.26  4870.2 1039.73  4893.1 1036.47    4906 1037.77
    4942 1035.93  4965.2 1035.58  4971.3 1036.67  4974.8 1035.29  4976.7 1034.54
  4978.2 1033.54  5038.2 1033.54  5039.7 1034.54    5045 1041.18  5065.2  1046.2
  5070.5 1044.75  5087.4 1048.13  5096.3 1048.64  5101.6 1046.27  5127.5 1049.04
  5132.8 1047.94  5160.6 1050.33  5226.2 1051.11  5371.7 1055.04  5542.5  1063.2
#Mann= 9 ,-1 , 0
  4526.5     .05       0    4639     .12       0    4813     .05       0
  4974.8     .12       0  4976.7     .07       0  5039.7     .12       0
  5160.6     .05       0  5226.2     .12       0  5371.7     .05       0
Bank Sta=4976.7,5039.7
XS Rating Curve= 0 ,0
Exp/Cntr=0.3,0.1