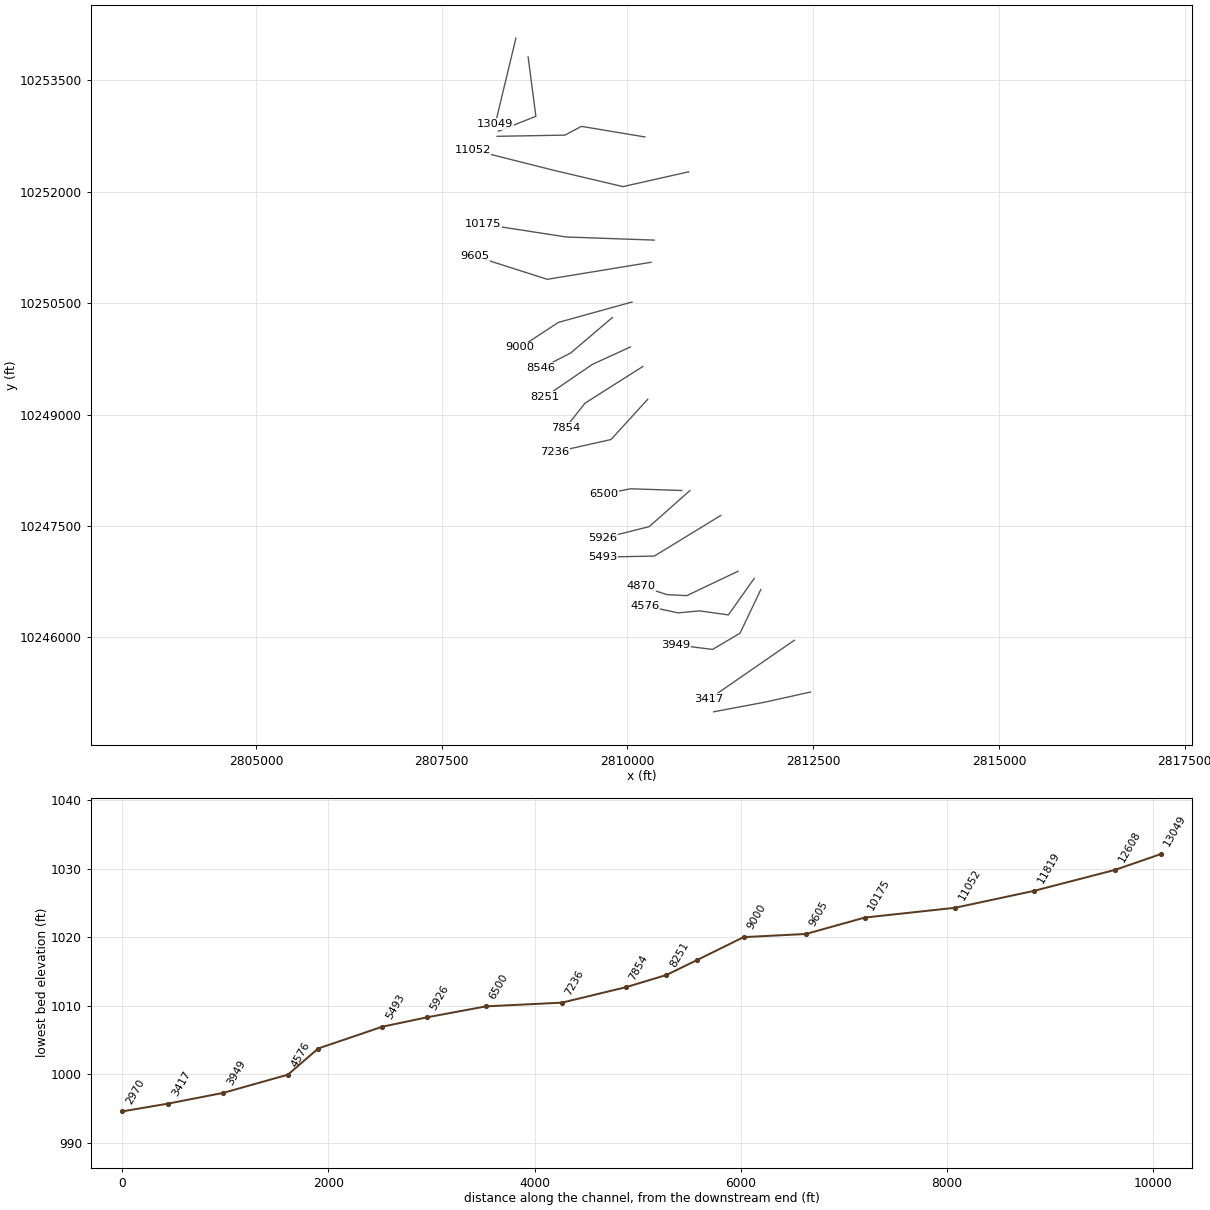
HEC-RAS study PECAN CREEK.prj: PECAN CREEK Base Level Engineering

--- PECAN CREEK.g01 (geometry) --- (continued)

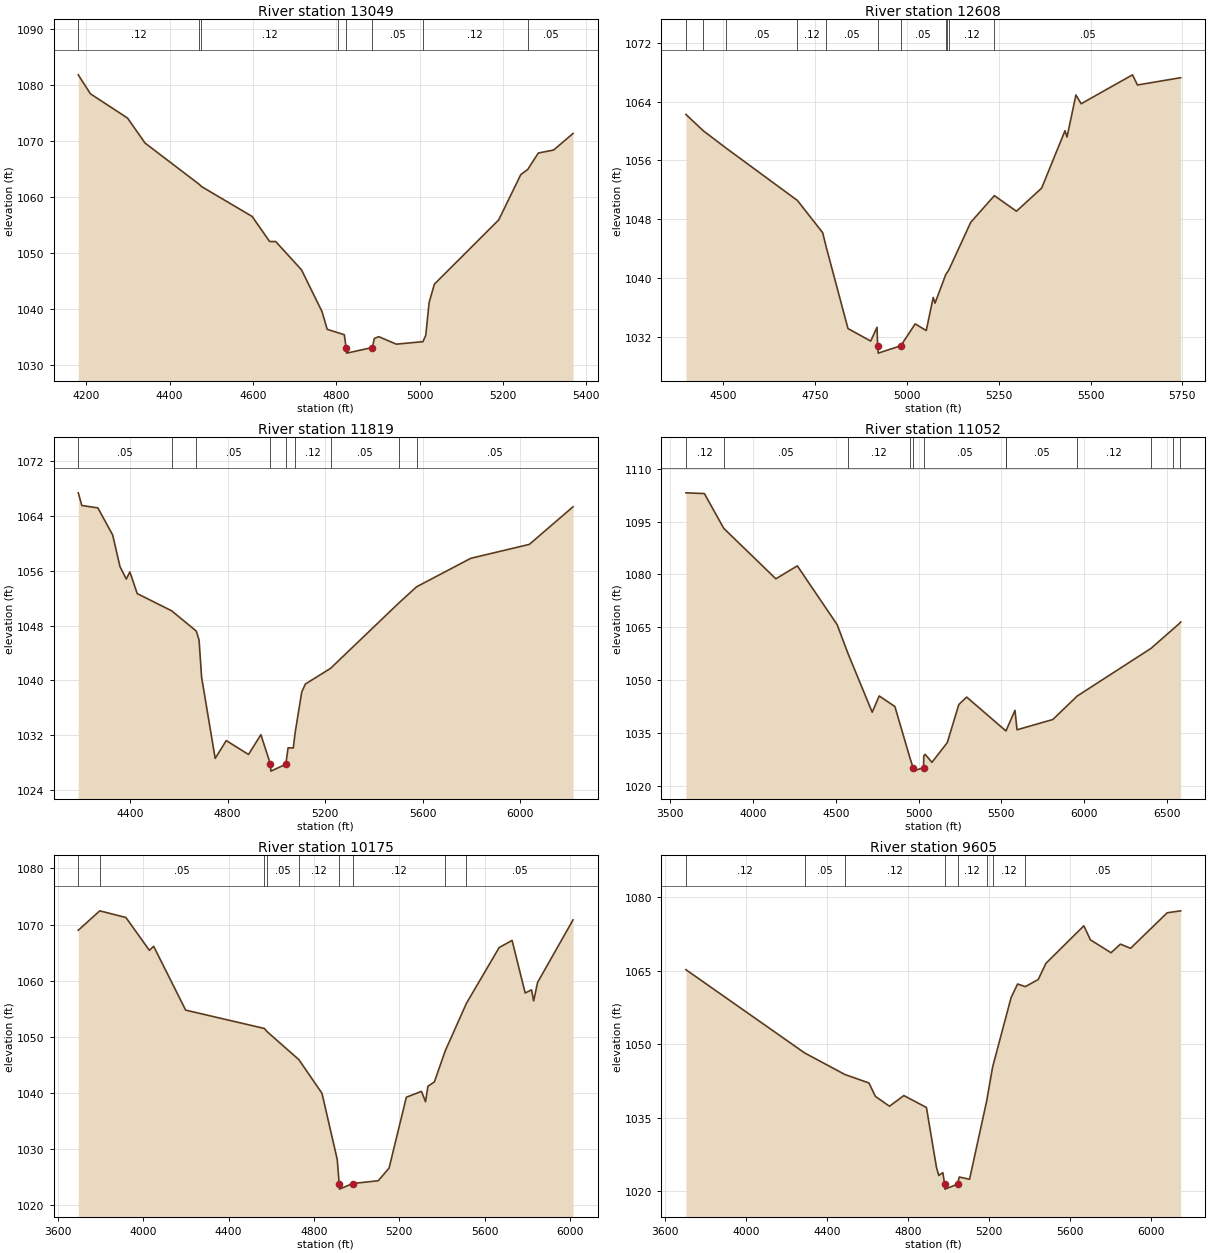
Type RM Length L Ch R = 1 ,13049   ,441,441,441
BEGIN DESCRIPTION:
Mapping XS 81545510
END DESCRIPTION:
XS GIS Cut Line= 2
      2808498.21     10254063.71      2808220.56     10252909.74
#Sta/Elev= 30
  4181.1 1081.82  4210.3 1078.43  4299.4 1074.09  4341.3 1069.63  4471.7 1062.24
  4476.6 1061.87  4598.1 1056.53  4640.1 1052.05  4654.8 1052.04  4716.6 1046.99
  4765.9 1039.52  4778.3 1036.36  4805.3 1035.73  4819.4 1035.39  4823.5 1033.11
    4825 1032.11  4886.5 1033.11  4891.4 1034.74    4902 1035.05    4944 1033.71
  5007.9 1034.16  5014.8 1035.32  5022.7 1041.12  5035.4 1044.43  5189.7  1055.9
  5242.7    1064  5259.2  1064.9  5284.7 1067.85  5321.5 1068.39    5368 1071.34
#Mann= 8 ,-1 , 0
  4181.1     .12       0  4471.7     .05       0  4476.6     .12       0
  4805.3     .05       0  4823.5     .05       0  4886.5     .05       0
  5007.9     .12       0  5259.2     .05       0
Bank Sta=4823.5,4886.5
XS Rating Curve= 0 ,0
Exp/Cntr=0.3,0.1

Type RM Length L Ch R = 1 ,12608   ,789,789,789
BEGIN DESCRIPTION:
Mapping XS 725c00fd
END DESCRIPTION:
XS GIS Cut Line= 3
      2808663.14     10253811.96      2808767.31     10253013.37
       2808263.8      10252813.7
#Sta/Elev= 30
  4398.4 1062.25  4445.9 1060.02  4508.7 1057.64    4702 1050.56  4770.7 1046.18
    4781 1044.11  4839.6 1033.16  4901.5 1031.46  4918.6 1033.33  4920.4 1030.82
  4921.9 1029.82  4983.4 1030.82  5022.5 1033.79  5052.7 1032.89  5071.6 1037.38
  5076.6 1036.61  5105.9 1040.51  5109.8 1040.79  5114.3 1041.14  5173.8 1047.59
  5238.2 1051.22  5298.2  1049.1  5366.9 1052.24  5430.5 1060.04  5435.9 1059.18
  5460.2 1064.89  5474.4  1063.7  5614.3 1067.63  5627.7 1066.25  5745.4 1067.24
#Mann= 11 ,-1 , 0
  4398.4     .05       0  4445.9     .12       0  4508.7     .05       0
    4702     .12       0    4781     .05       0  4920.4     .05       0
  4983.4     .05       0  5105.9     .12       0  5109.8     .05       0
  5114.3     .12       0  5238.2     .05       0
Bank Sta=4920.4,4983.4
XS Rating Curve= 0 ,0
Exp/Cntr=0.3,0.1

Type RM Length L Ch R = 1 ,11819   ,767,767,767
BEGIN DESCRIPTION:
PECAN CREEK 24.0
END DESCRIPTION:
XS GIS Cut Line= 4
       2810234.3     10252735.59      2809380.68     10252878.11
      2809158.13     10252760.29      2808246.42     10252744.27
#Sta/Elev= 30
  4187.9 1067.39  4202.5 1065.54  4268.3 1065.19  4329.1 1061.23  4358.9 1056.62
  4384.8  1054.8  4399.4 1055.84  4429.8 1052.67    4571 1050.16  4671.9  1047.2
  4683.3  1045.9  4693.7 1040.47  4749.4 1028.61  4794.8 1031.21  4886.1 1029.18
  4936.8 1032.07  4976.2 1027.75  4977.7 1026.75  5039.2 1027.75  5048.3 1030.15
  5069.7 1030.13  5077.1 1032.31  5104.3  1038.3  5119.3 1039.47  5222.7 1041.76
  5502.8 1051.31  5575.1 1053.66  5797.7 1057.83  6037.7 1059.86    6217 1065.35
#Mann= 9 ,-1 , 0
  4187.9     .05       0    4571     .12       0  4671.9     .05       0
  4976.2     .05       0  5039.2     .05       0  5077.1     .12       0
  5222.7     .05       0  5502.8     .12       0  5575.1     .05       0
Bank Sta=4976.2,5039.2
XS Rating Curve= 0 ,0
Exp/Cntr=0.3,0.1

Type RM Length L Ch R = 1 ,11052   ,877,877,877
BEGIN DESCRIPTION:
Mapping XS 4cef8410
END DESCRIPTION:
XS GIS Cut Line= 4
       2810824.6     10252266.84      2809939.18     10252067.19
      2809019.04      10252284.2      2807916.63     10252561.97
#Sta/Elev= 30
  3594.5 1103.13  3706.1 1102.92    3823 1093.07    4138 1078.77  4267.7 1082.44
  4508.5 1065.77  4574.3 1057.56  4720.2 1040.97  4762.5 1045.58  4857.4 1042.58
  4946.3 1028.35  4967.1 1025.28  4968.6 1024.28  5030.7 1025.28  5031.9 1028.58
    5040 1029.05  5081.1 1026.77  5173.6 1032.33  5243.6 1043.14    5291 1045.26
  5528.4 1035.67  5530.9 1035.94  5583.1  1041.5  5595.4 1035.99  5811.9 1038.91
  5958.6 1045.54  6404.8 1059.05    6535 1064.39  6578.4 1066.19  6584.4 1066.55
#Mann= 12 ,-1 , 0
  3594.5     .12       0    3823     .05       0  4574.3     .12       0
  4946.3     .05       0  4967.1     .03       0  5030.7     .05       0
  5528.4     .12       0  5530.9     .05       0  5958.6     .12       0
  6404.8     .05       0    6535     .12       0  6578.4     .05       0
Bank Sta=4967.1,5030.7
XS Rating Curve= 0 ,0
Exp/Cntr=0.3,0.1

Type RM Length L Ch R = 1 ,10175   ,570,570,570
BEGIN DESCRIPTION:
Mapping XS c98eff5e
END DESCRIPTION:
XS GIS Cut Line= 3
       2810358.9     10251347.68      2809178.38     10251389.34
      2808053.35     10251562.96
#Sta/Elev= 30
    3695 1068.99  3795.7 1072.45  3918.4 1071.26  4028.4 1065.41  4048.4 1066.13
  4198.5 1054.75    4568 1051.48  4580.2 1050.92  4729.5 1045.92  4837.6 1039.93
  4909.3 1028.12    4918 1023.85  4919.5 1022.85  4981.7 1023.85  5101.6 1024.35
  5152.2  1026.6  5233.1 1039.23    5304 1040.27  5323.1 1038.43  5334.3 1041.18
  5364.7 1041.97  5415.5  1047.5  5514.9 1055.97  5668.2  1065.9  5728.9 1067.18
  5790.4  1057.8    5820 1058.37  5830.1  1056.4  5848.5  1059.7  6014.6 1070.83
#Mann= 9 ,-1 , 0
    3695     .12       0  3795.7     .05       0    4568     .12       0
  4580.2     .05       0  4729.5     .12       0    4918     .05       0
  4981.7     .12       0  5415.5     .12       0  5514.9     .05       0
Bank Sta=4918,4981.7
XS Rating Curve= 0 ,0
Exp/Cntr=0.3,0.1

Type RM Length L Ch R = 1 ,9605    ,605,605,605
BEGIN DESCRIPTION:
Mapping XS f7ee744a
END DESCRIPTION:
XS GIS Cut Line= 3
      2810317.25     10251049.06      2808921.44      10250819.9
      2807942.29     10251132.39
#Sta/Elev= 30
  3704.6 1065.17  4290.9  1048.2  4489.6 1043.81  4608.1 1042.09  4639.9 1039.35
  4709.4 1037.35  4780.4 1039.52  4891.8  1037.1  4941.2 1024.93  4952.7 1023.25
  4972.9 1023.82  4981.6 1021.46  4983.1 1020.46  5045.3 1021.46    5054 1022.93
  5104.7 1022.47  5189.1 1038.39  5218.6 1045.35  5309.7 1059.48  5341.9 1062.25
    5380 1061.72  5443.7 1063.17    5482 1066.48    5669 1074.11  5701.2 1071.26
  5803.1 1068.62  5849.4 1070.37  5899.6 1069.53  6080.4 1076.76  6146.9 1077.16
#Mann= 8 ,-1 , 0
  3704.6     .12       0  4290.9     .05       0  4489.6     .12       0
  4981.6     .07       0  5045.3     .12       0  5189.1     .05       0
  5218.6     .12       0    5380     .05       0
Bank Sta=4981.6,5045.3
XS Rating Curve= 0 ,0
Exp/Cntr=0.3,0.1

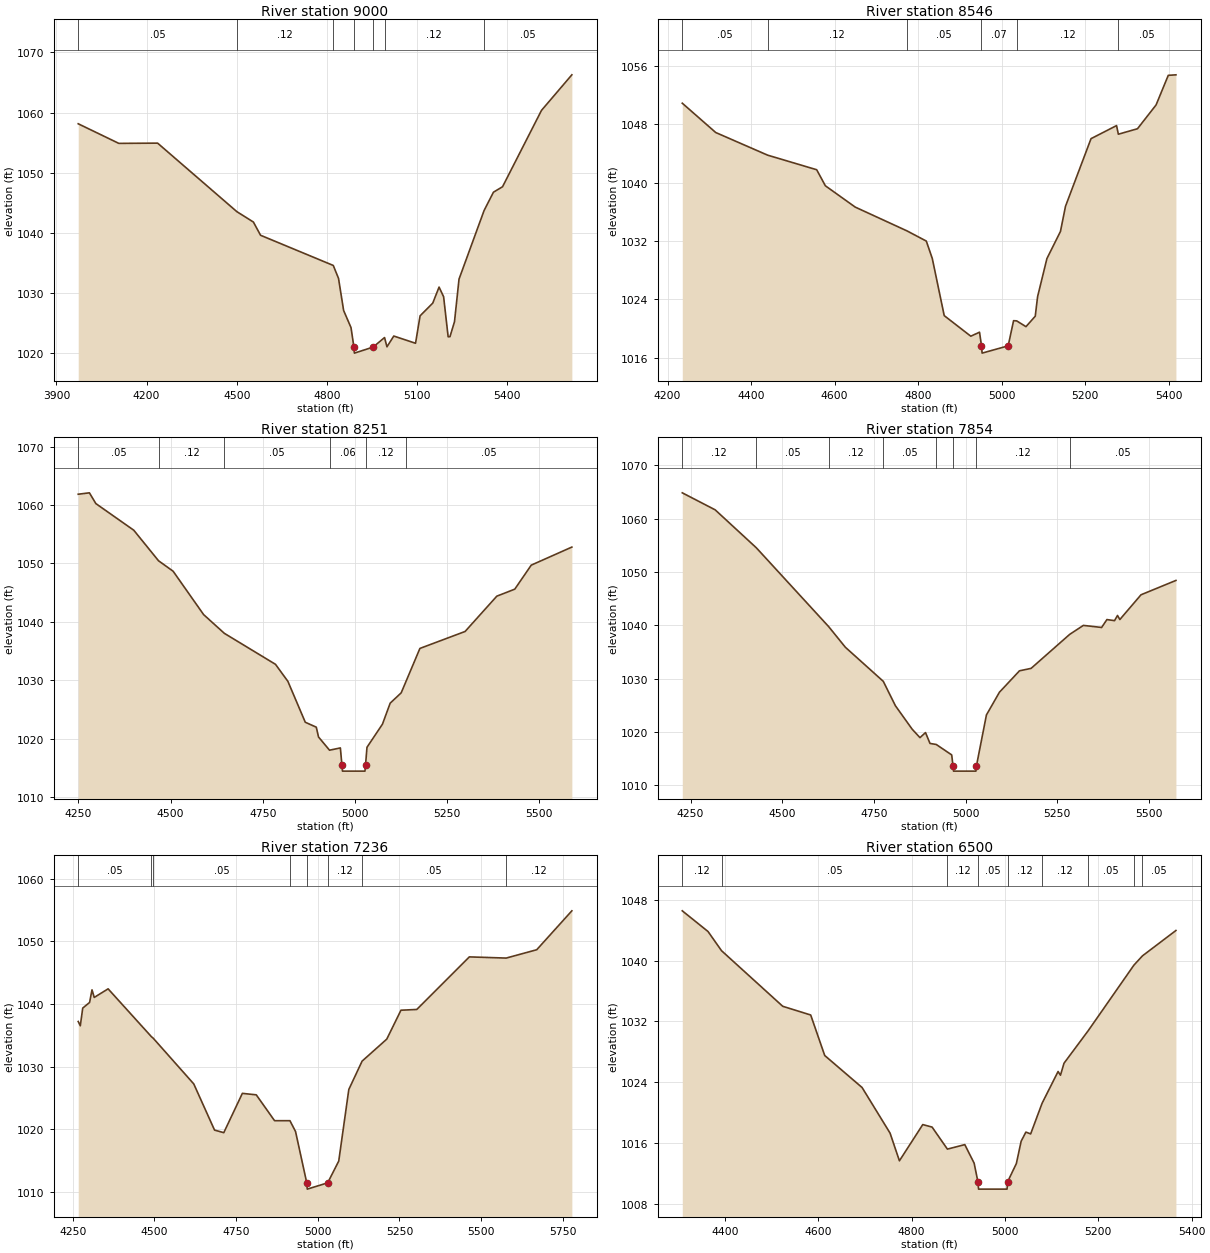
Type RM Length L Ch R = 1 ,9000    ,454,454,454
BEGIN DESCRIPTION:
PECAN CREEK 18.0
END DESCRIPTION:
XS GIS Cut Line= 3
      2810060.33     10250514.34      2809070.16     10250239.89
      2808555.69     10249903.11
#Sta/Elev= 30
  3972.5 1058.14  4107.6 1054.88  4236.7 1054.92  4500.2 1043.53  4555.3  1041.8
  4579.2  1039.6  4821.1 1034.58  4838.6 1032.42  4855.5  1027.1  4880.1 1024.24
  4889.8    1021  4891.3    1020  4953.5    1021  4991.7 1022.59  4999.7 1021.05
  5022.4 1022.84  5094.8 1021.64  5109.9  1026.2    5152 1028.31  5173.1 1030.98
  5188.2 1029.38  5203.3 1022.72  5209.3 1022.73  5224.4 1025.22  5239.5 1032.31
  5322.9 1043.72    5354 1046.76  5384.3 1047.67  5513.9 1060.37  5614.9 1066.28
#Mann= 7 ,-1 , 0
  3972.5     .05       0  4500.2     .12       0  4821.1     .05       0
  4889.8     .07       0  4953.5     .05       0  4991.7     .12       0
  5322.9     .05       0
Bank Sta=4889.8,4953.5
XS Rating Curve= 0 ,0
Exp/Cntr=0.3,0.1

Type RM Length L Ch R = 1 ,8546    ,295,295,295
BEGIN DESCRIPTION:
Mapping XS 0254c30b
END DESCRIPTION:
XS GIS Cut Line= 3
      2809796.41     10250305.99      2809233.94     10249826.84
      2808839.36     10249626.09
#Sta/Elev= 30
  4235.3  1050.9  4315.4 1046.88  4439.5 1043.78    4557 1041.78  4577.8 1039.58
  4649.2 1036.66  4773.4 1033.39  4819.4    1032  4833.7 1029.62  4862.3 1021.78
  4925.9 1018.96  4946.8 1019.51  4951.5 1017.64    4953 1016.64  5015.4 1017.64
  5028.3 1021.09  5035.7 1021.06    5058 1020.27  5080.2  1021.7  5085.8 1024.38
  5108.1  1029.6  5140.5 1033.32  5152.6 1036.77  5213.7 1046.04  5274.8 1047.83
  5279.1 1046.65  5324.9  1047.4  5369.4 1050.66  5398.6 1054.72  5416.9 1054.79
#Mann= 6 ,-1 , 0
  4235.3     .05       0  4439.5     .12       0  4773.4     .05       0
  4951.5     .07       0  5035.7     .12       0  5279.1     .05       0
Bank Sta=4951.5,5015.4
XS Rating Curve= 0 ,0
Exp/Cntr=0.3,0.1

Type RM Length L Ch R = 1 ,8251    ,397,397,397
BEGIN DESCRIPTION:
Mapping XS 7aea5d14
END DESCRIPTION:
XS GIS Cut Line= 3
      2810039.47     10249910.16       2809525.6     10249674.06
      2808887.82     10249237.32
#Sta/Elev= 30
  4249.6 1061.85  4279.9 1062.09  4297.4 1060.25  4400.3 1055.69  4467.3 1050.47
  4506.9 1048.68  4589.6 1041.26  4645.9 1038.05  4784.5 1032.75  4818.1 1029.84
  4865.3 1022.84  4895.1    1022  4901.2 1020.32    4931 1018.06  4960.4 1018.45
  4964.7 1015.48  4966.2 1014.48  5027.1 1014.48  5028.6 1015.48  5032.6 1018.56
  5074.5 1022.51  5095.5 1026.11  5125.3 1027.87  5137.3 1029.66  5176.1 1035.47
  5298.6 1038.37  5384.6 1044.41  5433.3 1045.61    5478 1049.72  5588.1 1052.81
#Mann= 6 ,-1 , 0
  4249.6     .05       0  4467.3     .12       0  4645.9     .05       0
    4931     .06       0  5028.6     .12       0  5137.3     .05       0
Bank Sta=4964.7,5028.6
XS Rating Curve= 0 ,0
Exp/Cntr=0.3,0.1

Type RM Length L Ch R = 1 ,7854    ,618,618,618
BEGIN DESCRIPTION:
Mapping XS 2fe189ba
END DESCRIPTION:
XS GIS Cut Line= 3
      2810206.17      10249646.3      2809428.38     10249153.23
      2809164.46     10248819.86
#Sta/Elev= 30
  4227.4 1064.87  4317.1 1061.68  4429.2 1054.57  4626.7 1039.77  4672.1 1035.91
  4775.5 1029.52  4808.5 1024.95  4854.3 1020.54  4875.5 1018.96  4890.7 1019.91
  4902.9 1017.87  4919.9 1017.68  4962.1 1015.72  4965.6 1013.68  4967.1 1012.68
  5028.1 1012.68  5029.6 1013.68  5056.8 1023.22  5092.3 1027.48  5146.9 1031.49
  5178.6 1031.95  5283.9 1038.33  5321.2 1040.01  5370.9 1039.62  5385.3  1041.1
  5406.1  1040.9  5414.2 1041.87  5420.6 1041.11  5478.3 1045.75  5573.5 1048.44
#Mann= 8 ,-1 , 0
  4227.4     .12       0  4429.2     .05       0  4626.7     .12       0
  4775.5     .05       0  4919.9     .12       0  4965.6     .07       0
  5029.6     .12       0  5283.9     .05       0
Bank Sta=4965.6,5029.6
XS Rating Curve= 0 ,0
Exp/Cntr=0.3,0.1

Type RM Length L Ch R = 1 ,7236    ,736,736,736
BEGIN DESCRIPTION:
PECAN CREEK 14.0
END DESCRIPTION:
XS GIS Cut Line= 3
      2810272.54     10249205.53      2809778.25       10248664.
      2809019.62     10248493.73
#Sta/Elev= 30
  4266.8 1037.19  4273.2 1036.51  4280.6 1039.33  4301.6 1040.23    4309 1042.24
  4315.8 1041.03  4358.3  1042.4  4490.9 1034.76    4496 1034.54  4620.4 1027.23
    4684 1019.86  4712.3 1019.45  4769.1 1025.72  4811.6 1025.49  4867.7 1021.36
  4914.7 1021.36  4931.9 1019.63  4966.2 1011.44  4967.7 1010.44  5030.2 1011.44
  5064.1 1014.92  5094.9 1026.34  5135.5 1030.86  5211.1 1034.38  5254.5 1038.99
  5302.9 1039.11  5463.8  1047.5  5576.5 1047.31    5670 1048.64  5777.5 1054.85
#Mann= 8 ,-1 , 0
  4266.8     .05       0  4490.9     .12       0    4496     .05       0
  4914.7     .12       0  4966.2     .07       0  5030.2     .12       0
  5135.5     .05       0  5576.5     .12       0
Bank Sta=4966.2,5030.2
XS Rating Curve= 0 ,0
Exp/Cntr=0.3,0.1

Type RM Length L Ch R = 1 ,6500    ,574,574,574
BEGIN DESCRIPTION:
PECAN CREEK 13.0
END DESCRIPTION:
XS GIS Cut Line= 3
      2810730.72     10247978.11      2810039.61     10248001.39
      2809680.71     10247928.12
#Sta/Elev= 30
  4308.5 1046.55  4363.6 1043.83  4392.6  1041.3  4523.7 1033.98  4583.7 1032.83
  4613.7  1027.5  4693.8 1023.28  4753.8 1017.27  4773.8 1013.63  4823.8  1018.4
  4843.8 1018.07  4876.6 1015.17  4913.9 1015.76  4933.9 1013.32  4941.9  1010.9
  4943.4  1009.9  5004.4  1009.9  5005.9  1010.9  5024.4 1013.27  5034.6  1016.2
  5044.8 1017.41    5055 1017.17  5079.6 1021.22  5113.8 1025.39  5118.9  1024.9
  5126.5 1026.48  5178.3 1030.76  5276.2 1039.39  5294.6 1040.62  5366.3 1043.96
#Mann= 9 ,-1 , 0
  4308.5     .12       0  4392.6     .05       0  4876.6     .12       0
  4941.9     .05       0  5005.9     .12       0  5079.6     .12       0
  5178.3     .05       0  5276.2     .12       0  5294.6     .05       0
Bank Sta=4941.9,5005.9
XS Rating Curve= 0 ,0
Exp/Cntr=0.3,0.1

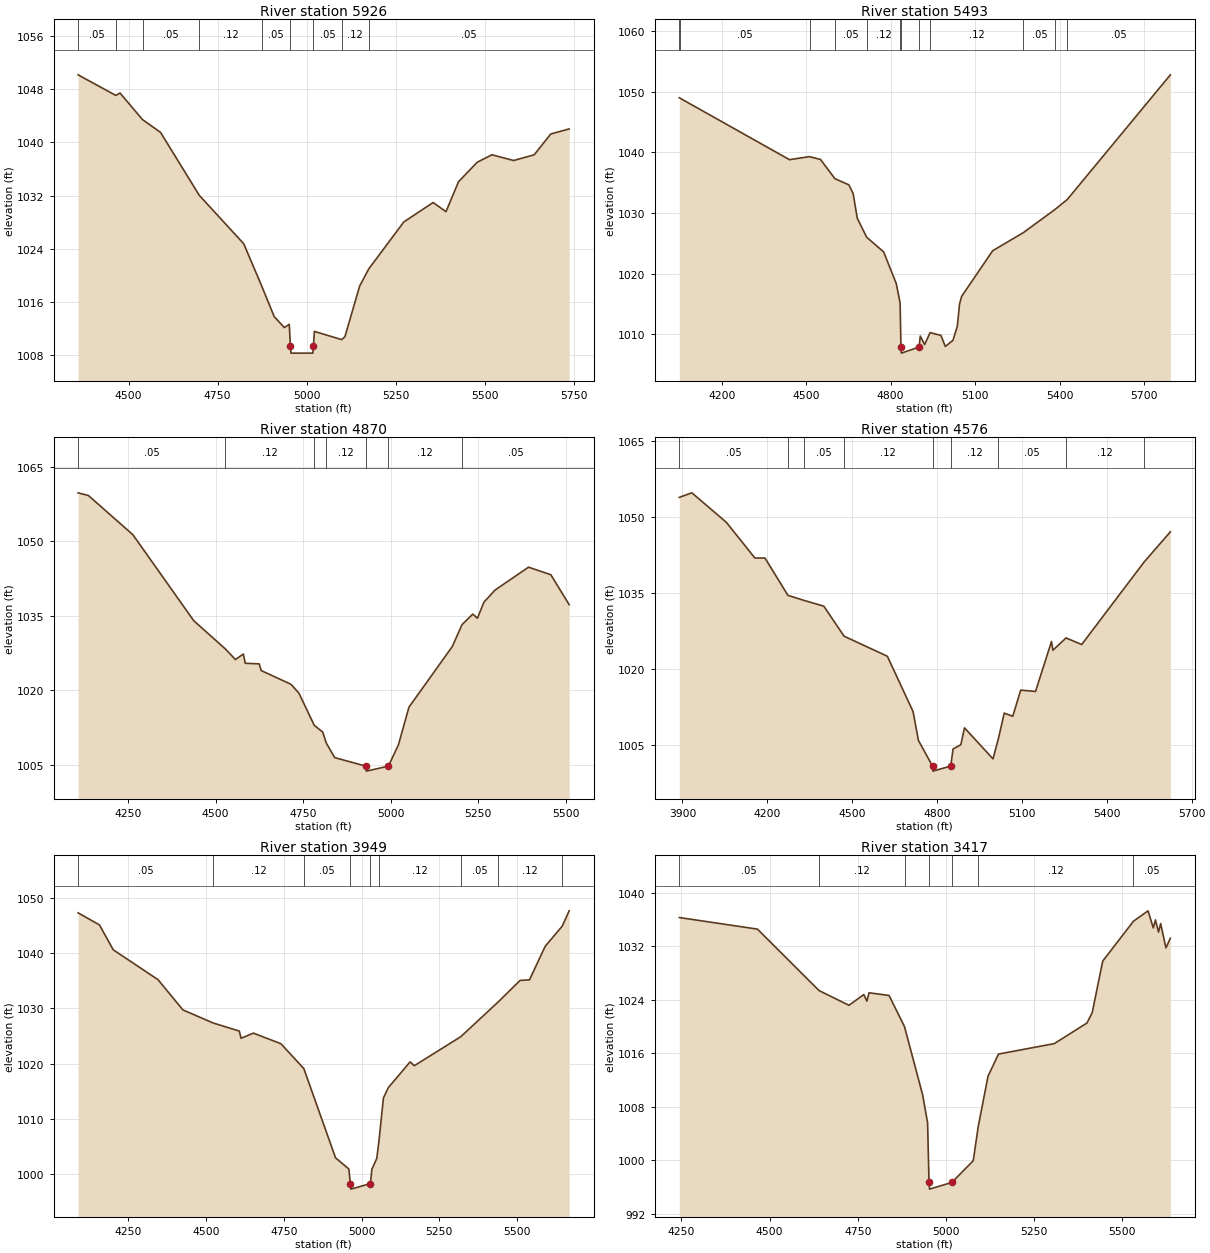
Type RM Length L Ch R = 1 ,5926    ,433,433,433
BEGIN DESCRIPTION:
Mapping XS ae0bf039
END DESCRIPTION:
XS GIS Cut Line= 3
      2810838.67     10247976.21       2810292.6     10247491.57
      2809664.64     10247334.58
#Sta/Elev= 30
  4358.6 1050.17  4464.5 1047.07  4476.2 1047.43  4539.4 1043.43  4589.9 1041.51
  4698.4 1032.05  4823.3 1024.75  4873.7 1018.39  4908.6  1013.8  4937.1 1012.15
  4950.9 1012.63  4954.2  1009.3  4955.7  1008.3  5017.1  1008.3  5018.6  1009.3
  5021.5 1011.57  5097.9 1010.33  5107.1 1010.78  5148.4 1018.39  5173.8 1020.96
  5272.1 1028.03  5354.5 1030.96  5390.6 1029.58  5425.7 1034.09  5478.2 1037.02
  5519.4 1038.14  5580.3 1037.28    5638 1038.14  5684.4 1041.27    5736 1042.03
#Mann= 9 ,-1 , 0
  4358.6     .05       0  4464.5     .12       0  4539.4     .05       0
  4698.4     .12       0  4873.7     .05       0  4954.2     .05       0
  5018.6     .05       0  5097.9     .12       0  5173.8     .05       0
Bank Sta=4954.2,5018.6
XS Rating Curve= 0 ,0
Exp/Cntr=0.3,0.1

Type RM Length L Ch R = 1 ,5493    ,623,623,623
BEGIN DESCRIPTION:
Mapping XS c12f06cf
END DESCRIPTION:
XS GIS Cut Line= 3
      2811255.09     10247641.75      2810360.86     10247095.66
      2809664.58       10247082.
#Sta/Elev= 30
  4049.5 1049.01  4053.3 1048.91  4440.8 1038.81  4512.1 1039.31  4551.1 1038.84
  4602.2 1035.68  4651.8 1034.66  4667.2 1033.19  4681.5 1029.17    4715 1026.03
  4775.3 1023.61  4820.1  1018.4  4833.8 1015.19  4836.8 1007.93  4838.3 1006.93
  4901.2 1007.93  4905.4 1009.75  4920.8 1008.34  4940.4 1010.31  4978.9 1009.85
  4994.3 1008.03  5021.5 1009.04    5037 1011.35  5044.8    1015  5052.4 1016.29
  5162.5  1023.8    5272  1026.8    5385 1030.64  5427.6 1032.25  5793.7 1052.79
#Mann= 12 ,-1 , 0
  4049.5     .12       0  4053.3     .05       0  4512.1     .12       0
  4602.2     .05       0    4715     .12       0  4833.8     .05       0
  4836.8     .07       0  4901.2     .05       0  4940.4     .12       0
    5272     .05       0    5385     .12       0  5427.6     .05       0
Bank Sta=4836.8,4901.2
XS Rating Curve= 0 ,0
Exp/Cntr=0.3,0.1

Type RM Length L Ch R = 1 ,4870    ,294,294,294
BEGIN DESCRIPTION:
Mapping XS 44474467
END DESCRIPTION:
XS GIS Cut Line= 4
      2811487.18     10246890.89      2810797.72     10246563.22
      2810531.51     10246576.88      2810176.52     10246692.93
#Sta/Elev= 30
  4106.8 1059.71  4136.3 1059.17  4263.5 1051.28  4437.2 1034.01  4527.2 1028.35
  4556.4 1026.19  4579.1 1027.29  4584.6 1025.44  4624.5 1025.31  4630.1 1023.97
  4715.4 1021.21  4738.1 1019.41  4781.8 1012.95    4806  1011.6  4816.2 1009.39
  4840.1 1006.47  4929.2 1004.75  4930.7 1003.75  4993.6 1004.75  5022.4 1009.06
  5052.4 1016.61  5176.3 1028.81    5204  1033.2  5234.8 1035.33  5248.1  1034.5
  5266.6 1037.72  5298.5 1040.16  5394.1 1044.76  5457.9 1043.24  5510.2 1037.23
#Mann= 7 ,-1 , 0
  4106.8     .05       0  4527.2     .12       0  4781.8     .05       0
  4816.2     .12       0  4929.2     .07       0  4993.6     .12       0
    5204     .05       0
Bank Sta=4929.2,4993.6
XS Rating Curve= 0 ,0
Exp/Cntr=0.3,0.1

Type RM Length L Ch R = 1 ,4576    ,627,627,627
BEGIN DESCRIPTION:
Mapping XS 8dcf30d9
END DESCRIPTION:
XS GIS Cut Line= 5
      2811705.61     10246795.34      2811357.46     10246303.83
      2810968.38     10246358.44      2810681.68     10246331.14
      2810239.33     10246426.41
#Sta/Elev= 30
    3889 1053.91  3933.4  1054.8  4055.2 1048.99  4156.1 1041.95  4191.8 1041.95
    4273 1034.58  4329.3  1033.6  4399.8 1032.45  4471.5 1026.53  4624.4 1022.58
  4715.3 1011.67  4734.2 1005.99    4784 1000.93  4785.5  999.93  4848.4 1000.93
  4856.6  1004.3  4884.2 1005.14    4897 1008.46  4997.8 1002.35  5016.9 1006.34
  5037.6 1011.37  5067.7 1010.75  5095.7  1015.9  5148.1 1015.64  5204.6 1025.49
  5209.7 1023.77    5256 1026.19  5311.3 1024.89  5531.4 1041.12  5624.7 1047.11
#Mann= 9 ,-1 , 0
    3889     .05       0    4273     .12       0  4329.3     .05       0
  4471.5     .12       0    4784     .07       0  4848.4     .12       0
  5016.9     .05       0    5256     .12       0  5531.4     .05       0
Bank Sta=4784,4848.4
XS Rating Curve= 0 ,0
Exp/Cntr=0.3,0.1

Type RM Length L Ch R = 1 ,3949    ,532,532,532
BEGIN DESCRIPTION:
Mapping XS 31af3b09
END DESCRIPTION:
XS GIS Cut Line= 4
      2811794.33     10246645.13      2811514.46      10246058.1
      2811145.85     10245839.66      2810649.12      10245900.9
#Sta/Elev= 30
  4088.3  1047.3    4157 1045.11  4201.3 1040.61  4345.3  1035.2  4425.3 1029.73
  4521.9 1027.37  4606.8 1025.89  4612.4 1024.59  4652.2 1025.52  4740.8  1023.6
  4814.4 1019.09  4916.3 1002.95  4959.1 1000.92    4964  998.28  4965.5  997.28
  5028.4  998.28  5033.2 1000.89  5048.9 1002.83  5055.9 1005.99  5070.3 1013.78
  5085.9 1015.64    5156 1020.31  5169.7 1019.62  5319.2 1024.88  5438.6 1031.12
  5509.8 1035.06  5540.1 1035.17  5590.5 1041.23  5645.4 1044.89  5667.6 1047.66
#Mann= 9 ,-1 , 0
  4088.3     .05       0  4521.9     .12       0  4814.4     .05       0
    4964     .05       0  5028.4     .05       0  5055.9     .12       0
  5319.2     .05       0  5438.6     .12       0  5645.4     .05       0
Bank Sta=4964,5028.4
XS Rating Curve= 0 ,0
Exp/Cntr=0.3,0.1

Type RM Length L Ch R = 1 ,3417    ,447,447,447
BEGIN DESCRIPTION:
Mapping XS 3f2e7dd2
END DESCRIPTION:
XS GIS Cut Line= 2
      2812244.86     10245962.54      2811099.39     10245171.62
#Sta/Elev= 30
  4244.1 1036.28  4465.5 1034.55  4640.3 1025.37  4725.1 1023.17    4767 1024.78
  4775.8  1023.8  4781.9 1025.04  4838.7 1024.64  4882.5 1019.98    4934 1009.77
  4947.9 1005.63    4952  996.72  4953.5  995.72  5016.7  996.72  5077.3  999.96
  5091.6 1005.09  5119.2 1012.58    5149 1015.89  5307.1 1017.45  5399.8 1020.53
  5414.6 1022.08  5444.4 1029.78  5531.6 1035.73  5572.8 1037.28  5587.7 1034.73
  5593.8 1035.92  5602.6  1034.1  5608.6 1035.38  5623.5 1031.75  5636.1 1033.19
#Mann= 7 ,-1 , 0
  4244.1     .05       0  4640.3     .12       0  4882.5     .05       0
    4952     .03       0  5016.7     .05       0  5091.6     .12       0
  5531.6     .05       0
Bank Sta=4952,5016.7
XS Rating Curve= 0 ,0
Exp/Cntr=0.3,0.1

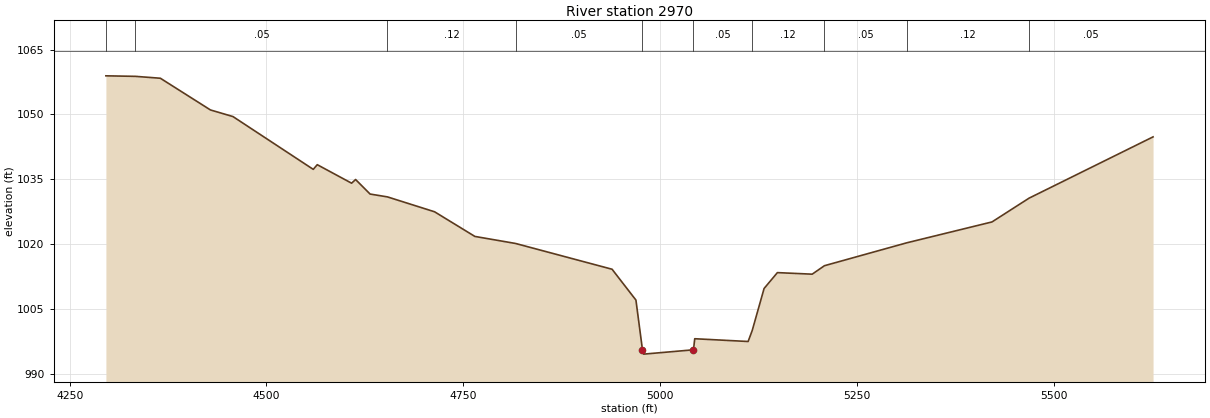
Type RM Length L Ch R = 1 ,2970    ,398,398,398
BEGIN DESCRIPTION:
Mapping XS fbc37166
END DESCRIPTION:
XS GIS Cut Line= 3
      2812463.26     10245266.27      2811848.94     10245129.75
      2811160.13     10245000.17
#Sta/Elev= 30
    4296 1058.94  4333.4 1058.82  4365.2 1058.38  4428.8 1051.05  4457.4 1049.52
  4559.4 1037.31  4564.5 1038.39  4608.1 1034.11  4613.2 1034.96  4631.6  1031.6
  4653.7 1030.94  4713.5  1027.5  4764.7  1021.8  4816.4 1020.17    4939 1014.21
  4969.3 1007.08  4977.6  995.58  4979.1  994.58  5042.4  995.58    5044  998.14
  5111.8   997.5    5117 1000.03  5132.1 1009.76    5149 1013.43  5193.2 1013.07
  5208.8 1015.03  5313.1 1020.31  5421.6 1025.15  5468.7 1030.65  5626.2 1044.82
#Mann= 10 ,-1 , 0
    4296     .12       0  4333.4     .05       0  4653.7     .12       0
  4816.4     .05       0  4977.6     .03       0  5042.4     .05       0
    5117     .12       0  5208.8     .05       0  5313.1     .12       0
  5468.7     .05       0
Bank Sta=4977.6,5042.4
XS Rating Curve= 0 ,0
Exp/Cntr=0.3,0.1