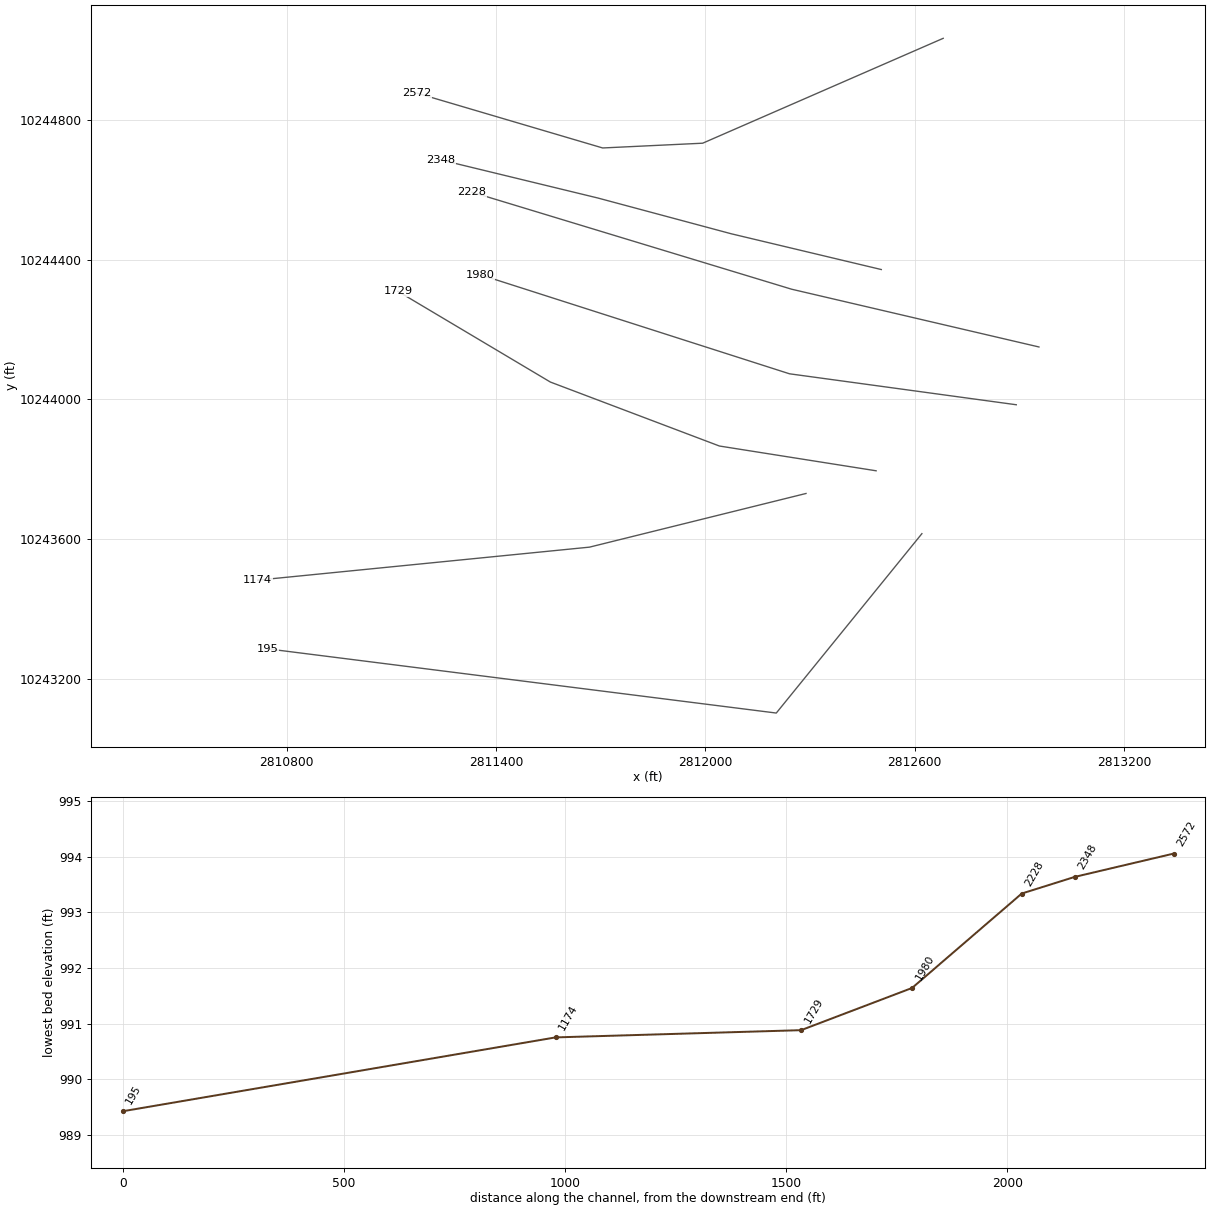
HEC-RAS study PECAN CREEK.prj: PECAN CREEK Base Level Engineering

--- PECAN CREEK.g01 (geometry) --- (continued)

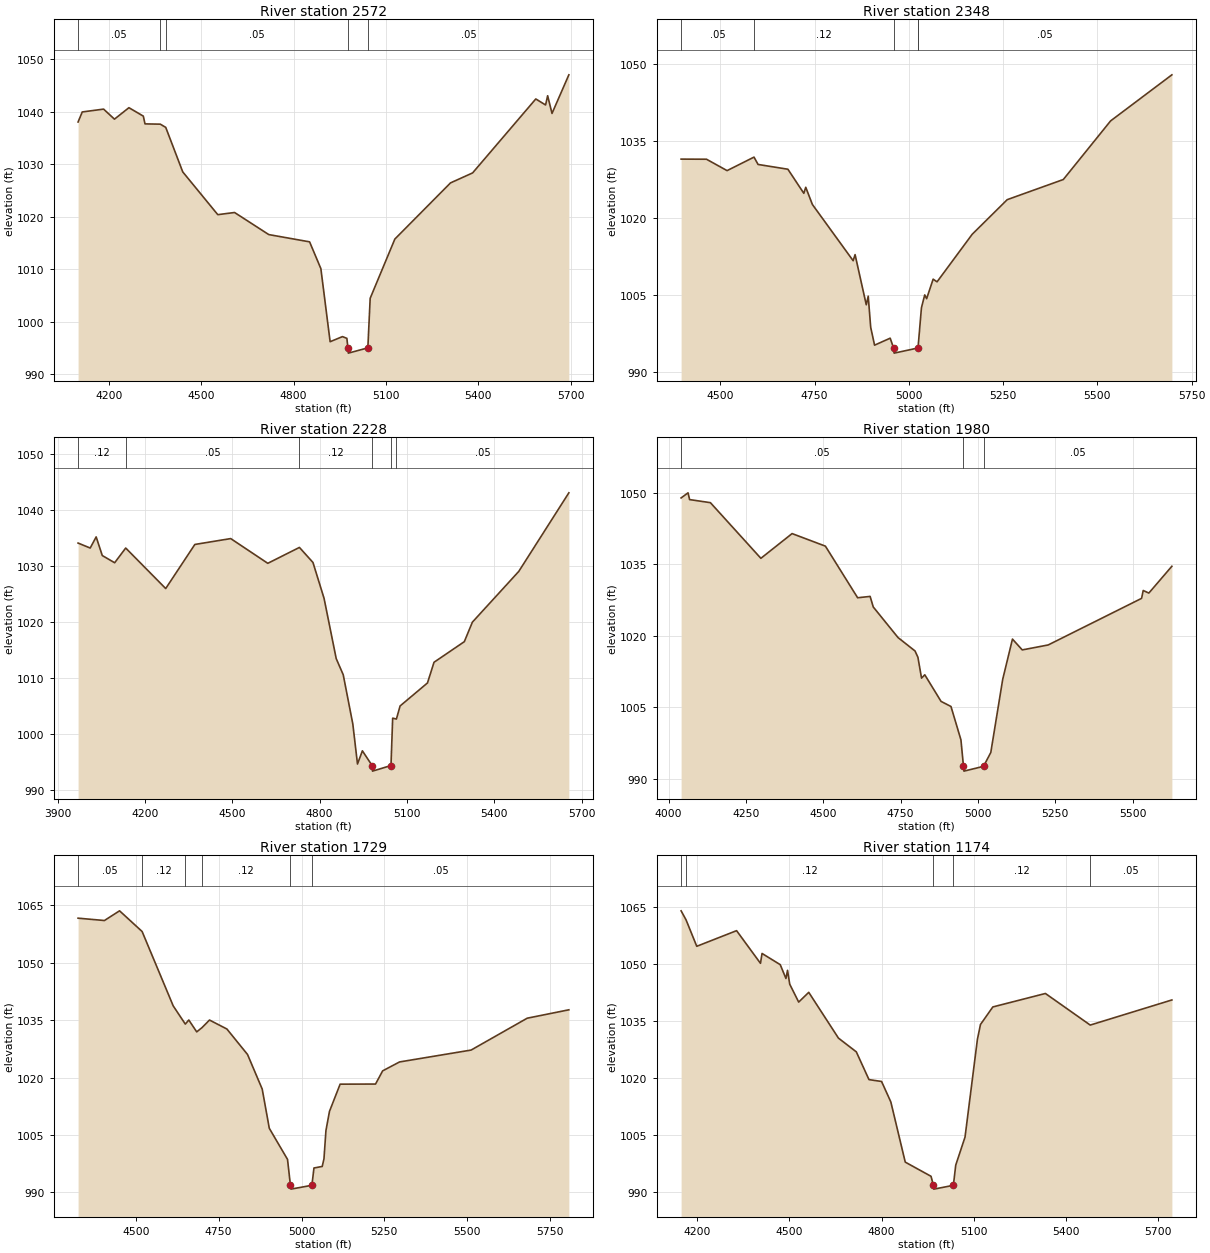
Type RM Length L Ch R = 1 ,2572    ,224,224,224
BEGIN DESCRIPTION:
Mapping XS 80076433
END DESCRIPTION:
XS GIS Cut Line= 4
       2812681.7     10245034.18      2811992.28     10244733.84
      2811705.59     10244720.19      2811173.17     10244877.18
#Sta/Elev= 30
    4100 1038.01  4113.6 1039.92  4182.9 1040.46  4218.2 1038.55  4265.1 1040.73
  4311.9 1039.13  4317.4 1037.65    4367  1037.6  4384.7 1036.99    4440 1028.52
  4553.8 1020.39  4608.3  1020.8  4719.5  1016.6    4852 1015.22  4888.6 1010.13
  4918.7  996.23  4958.7   997.2  4973.1  996.87  4976.4  995.06  4977.9  994.06
  5041.2  995.06  5048.8 1004.49  5128.9 1015.75  5309.7 1026.43  5381.5 1028.33
  5586.7 1042.39  5618.5 1041.25  5625.2    1043  5639.4 1039.64  5694.1 1046.98
#Mann= 5 ,-1 , 0
    4100     .05       0    4367     .12       0  4384.7     .05       0
  4976.4     .05       0  5041.2     .05       0
Bank Sta=4976.4,5041.2
XS Rating Curve= 0 ,0
Exp/Cntr=0.3,0.1

Type RM Length L Ch R = 1 ,2348    ,120,120,120
BEGIN DESCRIPTION:
Mapping XS 8aa1a4b3
END DESCRIPTION:
XS GIS Cut Line= 4
      2812504.27     10244372.05       2812074.2     10244474.45
      2811691.94     10244576.84      2811241.42     10244686.06
#Sta/Elev= 30
  4396.2 1031.41  4463.5 1031.39  4518.1 1029.17  4589.5  1031.8  4600.3 1030.37
  4679.4 1029.44  4721.6 1024.75  4726.7 1025.93  4744.3 1022.58  4852.4 1011.63
  4857.5 1012.82  4887.2 1003.05  4892.4 1004.72  4898.9  998.67  4909.2  995.19
  4950.6  996.55  4959.6  994.64  4961.1  993.64  5024.4  994.64  5025.4   995.5
  5033.5 1002.48  5042.2 1004.97  5047.3 1004.24  5064.5 1008.04  5074.9 1007.52
    5168 1016.77    5261 1023.52  5409.7 1027.44  5535.1 1038.85  5697.6 1047.82
#Mann= 5 ,-1 , 0
  4396.2     .05       0  4589.5     .12       0  4959.6     .07       0
  5024.4     .12       0  5025.4     .05       0
Bank Sta=4959.6,5024.4
XS Rating Curve= 0 ,0
Exp/Cntr=0.3,0.1

Type RM Length L Ch R = 1 ,2228    ,248,248,248
BEGIN DESCRIPTION:
Mapping XS 6dadad5e
END DESCRIPTION:
XS GIS Cut Line= 3
      2812956.19      10244150.3      2812247.07     10244315.76
      2811331.12      10244593.5
#Sta/Elev= 30
  3970.5 1034.11  4012.1 1033.22  4032.6 1035.21  4053.6 1031.88  4096.1 1030.59
  4134.1 1033.22  4271.4 1025.98  4371.5 1033.86  4494.7 1034.91    4622 1030.49
  4730.6 1033.33  4777.1 1030.64  4815.2 1024.22  4856.9 1013.46    4881 1010.57
  4913.9 1001.78    4930  994.61  4946.8  996.97  4980.2  994.34  4981.7  993.34
    5045  994.34  5050.8 1002.81  5063.6 1002.65  5076.3 1004.99  5170.3  1009.1
  5192.8  1012.8  5296.8 1016.48  5324.5 1019.97  5483.8 1029.04  5655.8 1043.09
#Mann= 6 ,-1 , 0
  3970.5     .12       0  4134.1     .05       0  4730.6     .12       0
  4980.2     .07       0    5045     .12       0  5063.6     .05       0
Bank Sta=4980.2,5045
XS Rating Curve= 0 ,0
Exp/Cntr=0.3,0.1

Type RM Length L Ch R = 1 ,1980    ,251,251,251
BEGIN DESCRIPTION:
Mapping XS b3b418b3
END DESCRIPTION:
XS GIS Cut Line= 3
      2812891.18     10243984.85      2812241.16     10244073.49
      2811354.77     10244357.13
#Sta/Elev= 30
  4040.6 1048.87    4063 1049.94  4068.1 1048.52  4135.3 1047.88  4298.5 1036.22
  4399.4  1041.4  4507.1 1038.77  4611.3 1027.96  4651.7 1028.24  4661.8 1026.03
  4741.9 1019.62  4796.9 1016.81  4806.2 1015.49  4817.9 1011.12  4828.4 1011.82
    4881 1006.25  4913.1 1005.18  4945.3  998.19  4953.5  992.64    4955  991.64
  5018.3  992.64  5041.8  995.54  5080.4 1010.89  5111.9  1019.3  5143.5 1017.03
  5227.4 1018.07  5529.3 1027.83  5534.6 1029.48  5552.8 1028.94  5627.3 1034.56
#Mann= 3 ,-1 , 0
  4040.6     .05       0  4953.5     .03       0  5018.3     .05       0
Bank Sta=4953.5,5018.3
XS Rating Curve= 0 ,0
Exp/Cntr=0.3,0.1

Type RM Length L Ch R = 1 ,1729    ,555,555,555
BEGIN DESCRIPTION:
Mapping XS 627a71e6
END DESCRIPTION:
XS GIS Cut Line= 4
      2812489.38     10243795.75      2812040.25     10243866.67
       2811555.7     10244049.85      2811118.47     10244309.83
#Sta/Elev= 30
  4325.6 1061.61  4405.1    1061  4450.8 1063.53  4518.9 1058.13  4612.8 1038.71
  4649.3 1033.96  4659.8 1035.03  4683.7 1031.93  4699.6 1033.03  4722.3 1035.02
  4774.8 1032.68  4837.1 1026.03  4881.4    1017  4902.8 1006.76  4957.8  998.64
  4966.6  991.88  4968.1  990.88  5031.4  991.88  5037.6   996.4  5062.5   996.8
  5067.8  998.77  5073.8 1006.19  5084.5 1011.19  5116.6 1018.28  5223.5 1018.31
  5244.9 1021.75  5295.9 1024.08  5511.9 1027.18  5681.3  1035.5    5807 1037.69
#Mann= 6 ,-1 , 0
  4325.6     .05       0  4518.9     .12       0  4649.3     .05       0
  4699.6     .12       0  4966.6     .07       0  5031.4     .05       0
Bank Sta=4966.6,5031.4
XS Rating Curve= 0 ,0
Exp/Cntr=0.3,0.1

Type RM Length L Ch R = 1 ,1174    ,979,979,979
BEGIN DESCRIPTION:
Mapping XS 6648b474
END DESCRIPTION:
XS GIS Cut Line= 3
      2812288.45     10243730.77      2811667.97     10243577.12
      2810716.57     10243482.58
#Sta/Elev= 30
  4148.5 1064.12  4164.6 1061.73  4199.4 1054.77  4328.8 1058.89  4406.5 1050.28
  4411.6 1052.88  4470.7 1049.93  4489.3 1046.28  4494.4 1048.43  4501.6 1044.77
  4530.7 1040.06  4563.4 1042.63    4660 1030.56    4718 1026.94  4759.2 1019.62
  4800.1 1019.13  4830.2 1013.74  4877.1  997.87  4960.9  994.13  4968.6  991.75
  4970.1  990.75  5033.5  991.75  5041.2  997.08  5071.4 1004.47  5111.6 1030.21
  5121.6 1034.15  5161.8 1038.78  5332.7 1042.33  5478.4    1034  5743.8 1040.62
#Mann= 5 ,-1 , 0
  4148.5     .05       0  4164.6     .12       0  4968.6     .07       0
  5033.5     .12       0  5478.4     .05       0
Bank Sta=4968.6,5033.5
XS Rating Curve= 0 ,0
Exp/Cntr=0.3,0.1

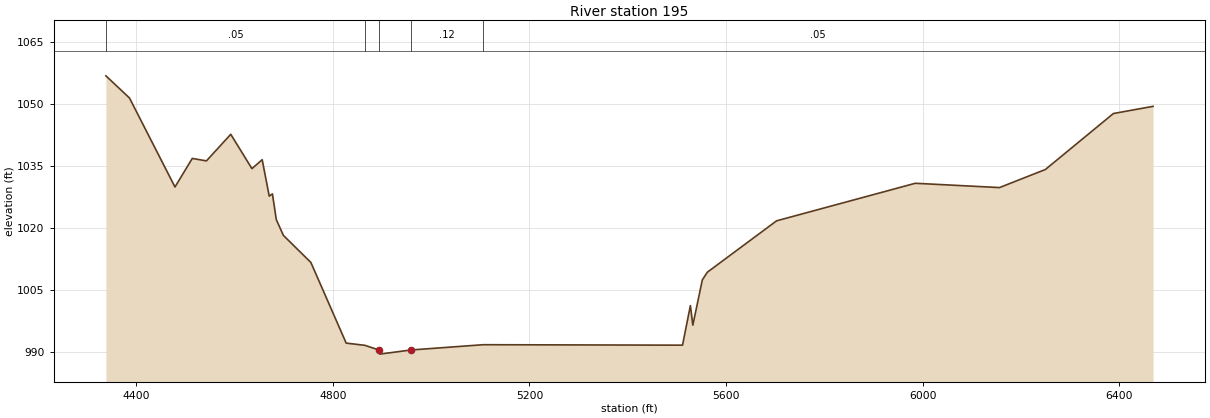
Type RM Length L Ch R = 1 ,195     ,0,0,0
BEGIN DESCRIPTION:
PECAN CREEK 1.0
END DESCRIPTION:
XS GIS Cut Line= 3
      2812620.64     10243615.71      2812203.25       10243102.
      2810745.59     10243285.82
#Sta/Elev= 30
  4338.1 1056.81  4386.1 1051.44  4478.7 1029.89  4513.9 1036.81  4542.7 1036.21
  4592.2 1042.65  4635.3 1034.34  4656.2  1036.5  4670.5 1027.68    4677 1028.23
  4684.9 1021.99  4699.3 1018.18  4755.3 1011.61  4827.1  992.09  4865.2  991.55
  4893.8  990.42  4895.3  989.42  4958.7  990.42  5105.8   991.7  5511.6  991.59
  5527.6 1001.17  5532.6  996.44  5551.9 1007.38    5562 1009.24  5703.1  1021.7
  5985.3 1030.79  6156.7 1029.75  6250.1 1034.13  6388.5 1047.68  6469.2 1049.42
#Mann= 5 ,-1 , 0
  4338.1     .05       0  4865.2     .12       0  4893.8     .07       0
  4958.7     .12       0  5105.8     .05       0
Bank Sta=4893.8,4958.7
XS Rating Curve= 0 ,0
Exp/Cntr=0.3,0.1

Chan Stop Cuts=-1
Use User Specified Reach Order=0
Composite Channel Slope=5