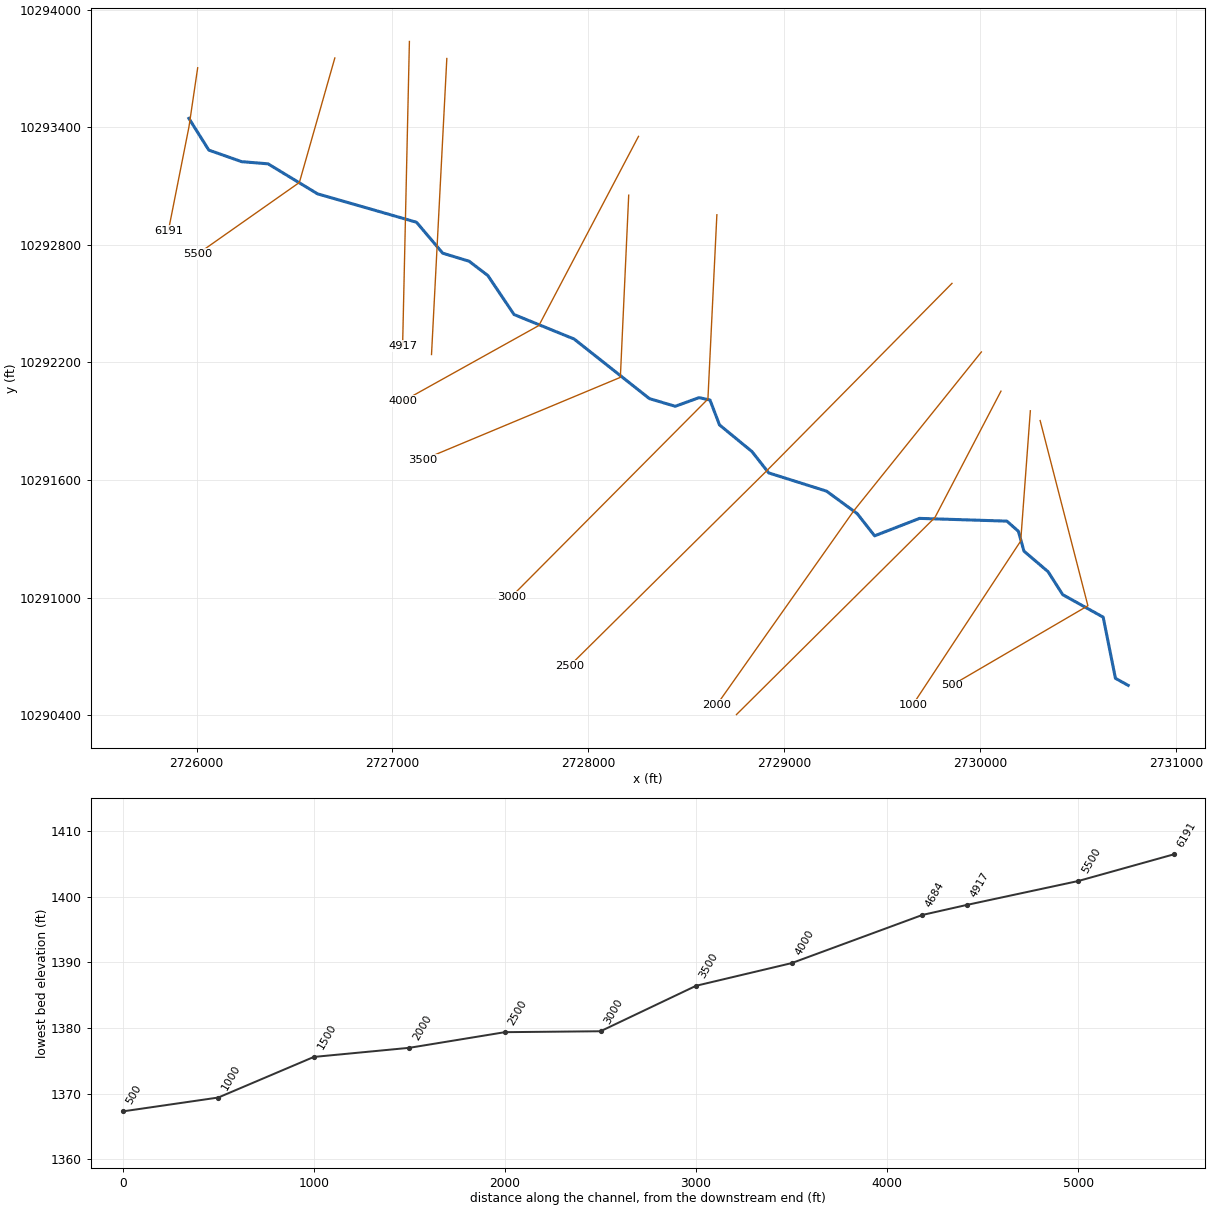
--- PONTOTOC CREEK.prj (project) ---

Proj Title=PONTOTOC CREEK Base Level Engineering
Current Plan=p01
Default Exp/Contr=0.3,0.1
English Units
Geom File=g01
Flow File=f01
Plan File=p01
Y Axis Title=Elevation
X Axis Title(PF)=Main Channel Distance
X Axis Title(XS)=Station
BEGIN DESCRIPTION:
PONTOTOC CREEK
END DESCRIPTION:
DSS Export Rating Curves= 0
DSS Export Rating Curve Sorted= 0
DSS Export Volume Flow Curves= 0
DXF OffsetX= 0
DXF OffsetY= 0
DXF ScaleX= 1
DXF ScaleY= 10

--- PONTOTOC CREEK.p01 (plan) ---

Plan Title=Multiple Run
Short Identifier=Multiple
Geom File=g01
Flow File=f01
Subcritical Flow
K Sum by GR= 0
Std Step Tol= 0.01
Critical Tol= 0.01
Num of Std Step Trials= 20
Max Error Tol= 0.3
Flow Tol Ratio= 0.001
Split Flow NTrial= 30
Split Flow Tol= 0.02
Split Flow Ratio= 0.02
Log Output Level= 0
Friction Slope Method= 1
Unsteady Friction Slope Method= 2
Unsteady Bridges Friction Slope Method= 1
Parabolic Critical Depth
Global Vel Dist=  1 , 1 , 1
Global Log Level= 0
CheckData=True
Encroach Param= -1, 0, 0, 0
BEGIN DESCRIPTION:
Multiple Run
END DESCRIPTION:

--- PONTOTOC CREEK.f01 (steady flow) ---

Flow Title=Multiple
Program Version=4.10
Number of Profiles= 7
Profile Names=10-year,25-year,50-year,1pct_min,100-year,1pct_plu,500-year
River Rch & RM=PONTOTOC CREEK,Reach-1         ,6191
    1833    3279    6625    5800    9713   16267   13932
Boundary for River Rch & Prof#=PONTOTOC CREEK,Reach-1         , 1
Up Type= 0
Dn Type= 3
Dn Slope=0.005
Boundary for River Rch & Prof#=PONTOTOC CREEK,Reach-1         , 2
Up Type= 0
Dn Type= 3
Dn Slope=0.005
Boundary for River Rch & Prof#=PONTOTOC CREEK,Reach-1         , 3
Up Type= 0
Dn Type= 3
Dn Slope=0.005
Boundary for River Rch & Prof#=PONTOTOC CREEK,Reach-1         , 4
Up Type= 0
Dn Type= 3
Dn Slope=0.005
Boundary for River Rch & Prof#=PONTOTOC CREEK,Reach-1         , 5
Up Type= 0
Dn Type= 3
Dn Slope=0.005
Boundary for River Rch & Prof#=PONTOTOC CREEK,Reach-1         , 6
Up Type= 0
Dn Type= 3
Dn Slope=0.005
Boundary for River Rch & Prof#=PONTOTOC CREEK,Reach-1         , 7
Up Type= 0
Dn Type= 3
Dn Slope=0.005
DSS Import GetInterval= 0
DSS Import GetPeak= 0
DSS Import FillOption= 0

--- PONTOTOC CREEK.g01 (geometry) ---

Geom Title=Existing Conditions
Program Version=4.10

River Reach=PONTOTOC CREEK  ,Reach-1
Reach XY= 30
      2725960.75       10293445.       2726062.5       10293283.
       2726230.5       10293224.      2726364.75       10293213.
      2726617.25       10293060.       2727122.5       10292915.
       2727256.5       10292757.      2727391.25       10292716.
      2727486.75       10292643.       2727620.5       10292444.
      2727927.25       10292319.       2728311.5       10292015.
      2728443.25       10291976.      2728564.75       10292020.
       2728620.5       10292008.        2728669.       10291881.
      2728834.75       10291745.      2728920.25       10291636.
       2729215.5       10291543.      2729372.25       10291428.
      2729460.75       10291315.        2729690.       10291404.
        2730136.       10291390.      2730194.75       10291338.
        2730223.       10291237.      2730346.25       10291132.
      2730420.75       10291015.       2730627.5       10290900.
        2730690.       10290588.        2730755.       10290552.

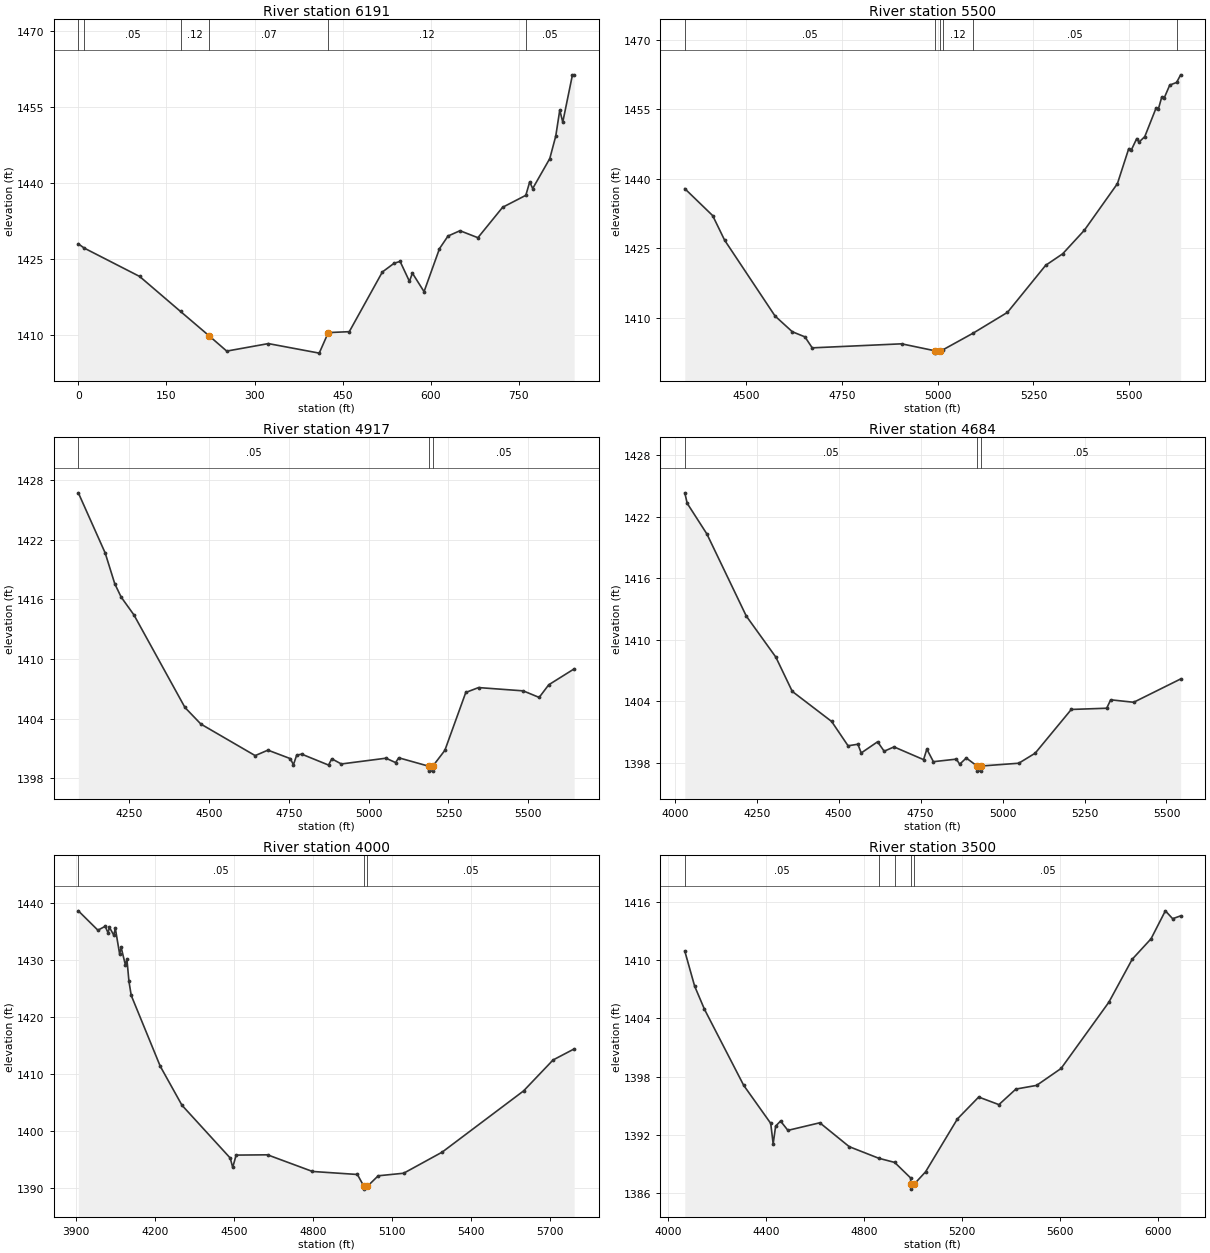
Type RM Length L Ch R = 1 ,6191    ,500,500,500
BEGIN DESCRIPTION:
PONTOTOC CREEK 12.0
END DESCRIPTION:
XS GIS Cut Line= 3
      2726005.68     10293703.11       2725961.2      10293401.8
      2725856.28      10292872.4
#Sta/Elev= 30
       0 1427.97    10.1 1427.13   104.4 1421.54     174 1414.64   222.4 1409.86
   252.7 1406.82   323.6  1408.3   410.2 1406.42   425.6 1410.47   461.4 1410.65
   517.7 1422.42   537.7 1424.14   547.9 1424.51   563.8 1420.58   568.9 1422.19
   588.7 1418.54     615 1427.03   629.5 1429.51   649.9 1430.56   680.4 1429.18
   722.5 1435.18     762 1437.54   768.6 1440.19   773.7 1438.88   802.8 1444.79
     813 1449.24   819.8 1454.35   824.9 1451.97   841.4  1461.3   844.3  1461.3
#Mann= 6 ,-1 , 0
       0     .12       0    10.1     .05       0     174     .12       0
   222.4     .07       0   425.6     .12       0     762     .05       0
Bank Sta=222.4,425.6
XS Rating Curve= 0 ,0
Exp/Cntr=0.3,0.1

Type RM Length L Ch R = 1 ,5500    ,583,583,583
BEGIN DESCRIPTION:
PONTOTOC CREEK 11.0
END DESCRIPTION:
XS GIS Cut Line= 3
      2726705.69     10293753.15       2726524.8      10293117.9
      2726005.66      10292753.1
#Sta/Elev= 30
  4339.5 1437.89  4412.3 1432.07  4443.5 1426.76  4575.2 1410.38  4620.3 1406.98
  4653.3 1405.87  4672.3  1403.5  4905.8 1404.37  4993.2 1402.86  4993.7 1402.36
  5006.6 1402.86    5014 1403.09  5093.1  1406.7  5182.3 1411.17    5282 1421.33
  5326.5 1423.82  5383.1 1428.91  5469.4 1438.97    5499 1446.54  5505.1 1446.14
  5519.9 1448.71    5526 1447.96  5540.8 1449.12  5570.4 1455.31  5576.5 1455.12
  5585.2 1457.68  5591.3 1457.42  5606.1 1460.27    5624 1460.83  5634.5 1462.48
#Mann= 6 ,-1 , 0
  4339.5     .05       0  4993.2     .05       0  5006.6     .05       0
    5014     .12       0  5093.1     .05       0    5624     .12       0
Bank Sta=4993.2,5006.6
XS Rating Curve= 0 ,0
Exp/Cntr=0.3,0.1

Type RM Length L Ch R = 1 ,4917    ,233,233,233
BEGIN DESCRIPTION:
Mapping XS c8ea9ff4
END DESCRIPTION:
XS GIS Cut Line= 2
      2727086.34     10293837.26      2727051.62     10292283.45
#Sta/Elev= 30
  4089.8  1426.7    4174 1420.65    4204 1417.56    4224 1416.22    4264 1414.43
    4424 1405.12    4474 1403.45  4644.1 1400.28  4684.1 1400.83  4754.1 1399.98
  4764.1 1399.36  4774.1 1400.32  4789.8 1400.43  4874.1 1399.33  4884.2 1399.96
  4914.2 1399.44  5054.2 1400.02  5084.2 1399.58  5094.2 1400.06  5187.5 1399.22
    5188 1398.72  5200.4 1398.72  5200.9 1399.22  5238.7 1400.81  5304.3 1406.63
  5344.3 1407.12  5484.3 1406.79  5534.3 1406.13  5564.3  1407.4    5644    1409
#Mann= 3 ,-1 , 0
  4089.8     .05       0  5187.5     .05       0  5200.9     .05       0
Bank Sta=5187.5,5200.9
XS Rating Curve= 0 ,0
Exp/Cntr=0.3,0.1

Type RM Length L Ch R = 1 ,4684    ,684,684,684
BEGIN DESCRIPTION:
Mapping XS df668c98
END DESCRIPTION:
XS GIS Cut Line= 2
      2727277.31     10293750.45      2727199.19     10292240.07
#Sta/Elev= 30
  4030.8 1424.31  4038.1 1423.29  4098.2  1420.3  4218.4  1412.3  4308.5  1408.3
  4358.6 1404.96  4478.7 1402.03  4528.8 1399.66  4558.8 1399.81  4568.9 1398.96
  4618.9 1400.05  4638.9 1399.13    4669 1399.55  4759.1 1398.31  4769.1 1399.33
  4789.1 1398.11  4859.2 1398.36  4869.3 1397.86  4889.3 1398.47  4922.2 1397.69
  4922.7 1397.19  4935.1 1397.19  4935.6 1397.69  5049.5 1397.96  5099.6 1398.94
  5209.7  1403.2  5317.7 1403.32  5329.9 1404.14    5400  1403.9  5543.2 1406.17
#Mann= 3 ,-1 , 0
  4030.8     .05       0  4922.2     .05       0  4935.6     .05       0
Bank Sta=4922.2,4935.6
XS Rating Curve= 0 ,0
Exp/Cntr=0.3,0.1

Type RM Length L Ch R = 1 ,4000    ,500,500,500
BEGIN DESCRIPTION:
PONTOTOC CREEK 8.0
END DESCRIPTION:
XS GIS Cut Line= 3
      2728255.69     10293353.12      2727747.25     10292388.06
      2727055.67     10292003.11
#Sta/Elev= 30
  3909.2 1438.69  3983.5 1435.29  4011.2 1435.98  4021.9 1434.83  4027.5 1435.78
  4043.9 1434.41  4049.6 1435.63    4066  1431.1  4071.6 1432.29    4088 1429.17
  4093.6 1430.21  4101.4  1426.3    4110 1423.85  4220.2 1411.42  4302.6 1404.58
  4485.7 1395.32  4495.3 1393.68  4508.3 1395.83  4627.4 1395.88    4798 1392.96
  4968.6 1392.43  4993.2 1390.36  4993.7 1389.86  5006.7 1390.36  5047.6  1392.2
  5144.3 1392.65  5290.7 1396.36  5599.4 1407.09  5711.4 1412.52  5791.5 1414.46
#Mann= 3 ,-1 , 0
  3909.2     .05       0  4993.2     .03       0  5006.7     .05       0
Bank Sta=4993.2,5006.7
XS Rating Curve= 0 ,0
Exp/Cntr=0.3,0.1

Type RM Length L Ch R = 1 ,3500    ,500,500,500
BEGIN DESCRIPTION:
PONTOTOC CREEK 7.0
END DESCRIPTION:
XS GIS Cut Line= 3
      2728205.68     10293053.12      2728163.03      10292123.5
      2727155.72     10291703.13
#Sta/Elev= 30
  4069.4 1410.91  4109.5 1407.31  4149.5 1404.93  4309.7 1397.09  4419.8 1393.18
  4429.8 1391.07  4439.8 1392.89  4459.8 1393.42  4489.9 1392.46    4620 1393.24
  4740.1 1390.78  4860.2 1389.59  4925.3 1389.16  4990.4 1387.56  4990.9 1386.91
  4991.4 1386.41  5004.4 1386.91  5051.3 1388.19  5181.3 1393.64    5268 1395.89
  5350.4 1395.11  5419.7 1396.71  5504.2 1397.09  5603.9 1398.83    5799 1405.66
  5893.9 1410.07  5970.8 1412.18  6029.3 1415.06    6059 1414.25  6091.5 1414.54
#Mann= 5 ,-1 , 0
  4069.4     .05       0  4860.2     .12       0  4925.3     .05       0
  4990.9     .05       0  5004.4     .05       0
Bank Sta=4990.9,5004.4
XS Rating Curve= 0 ,0
Exp/Cntr=0.3,0.1

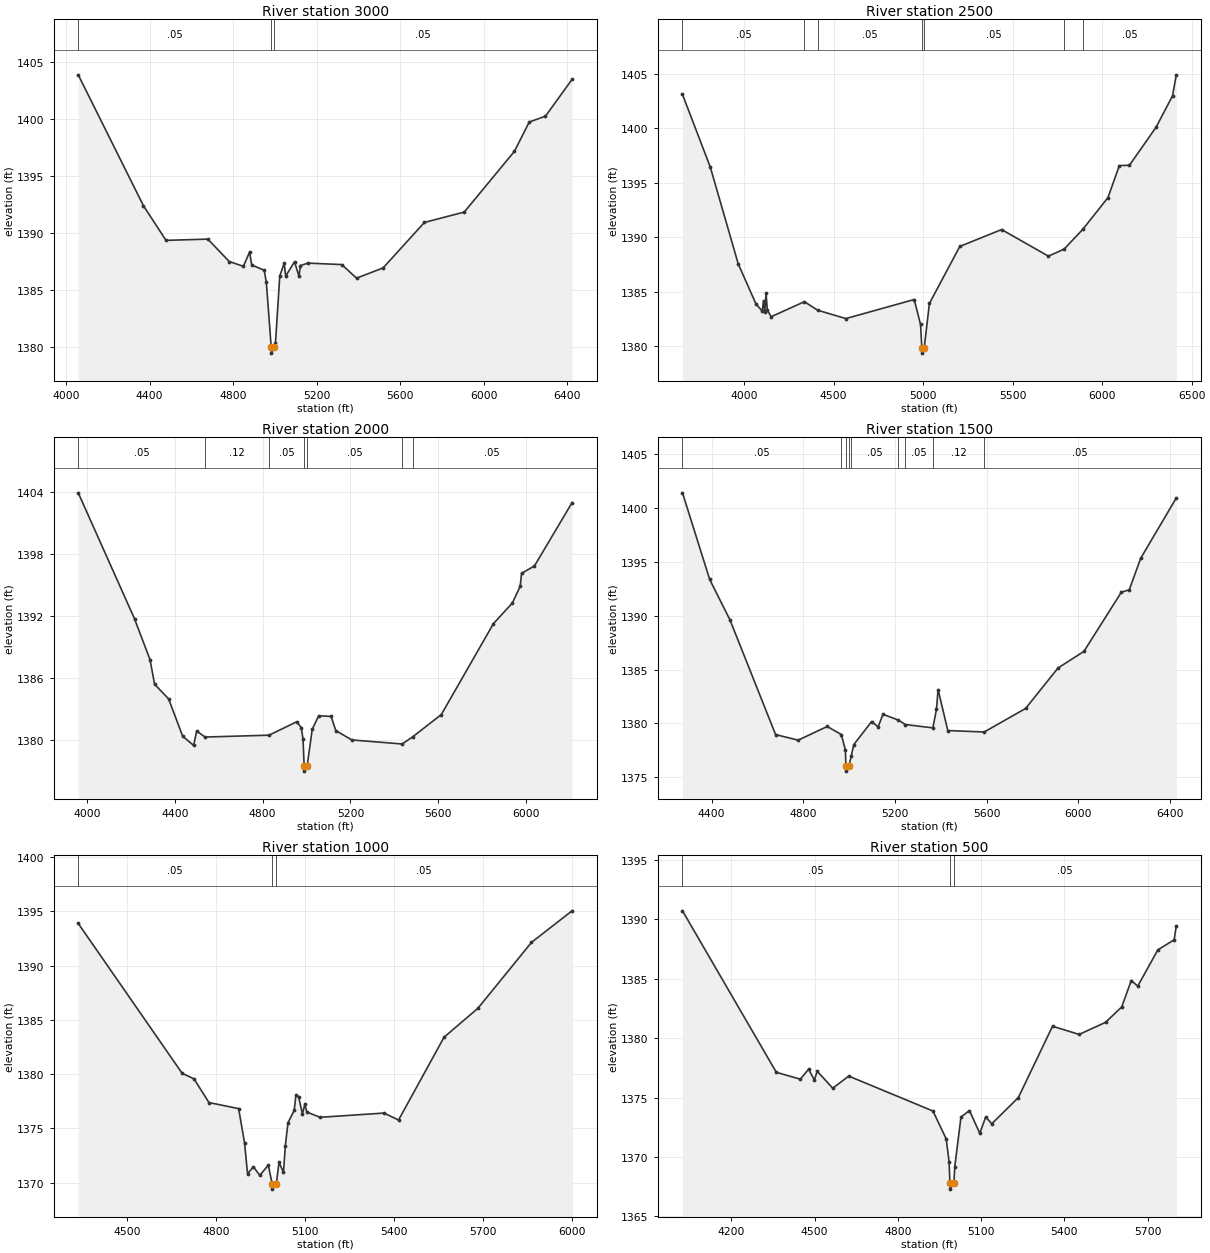
Type RM Length L Ch R = 1 ,3000    ,500,500,500
BEGIN DESCRIPTION:
PONTOTOC CREEK 6.0
END DESCRIPTION:
XS GIS Cut Line= 3
      2728655.68     10292953.11      2728609.96     10292012.82
      2727605.69     10291003.12
#Sta/Elev= 30
  4058.6 1403.85  4370.7  1392.4  4479.1 1389.36  4679.3 1389.47  4781.8 1387.51
  4849.5 1387.09  4879.6 1388.34  4889.6 1387.21  4949.6 1386.74  4959.7 1385.68
  4983.1 1379.99  4983.6 1379.49  4996.7 1379.99  5003.3 1380.34    5024 1386.24
  5045.2 1387.36  5052.3 1386.23  5094.7 1387.49  5115.9 1386.22    5123 1387.15
  5158.4 1387.37    5321 1387.24  5391.7 1386.05    5519 1386.95    5717 1390.93
  5907.9 1391.84  6148.3 1397.16    6219 1399.72  6296.8 1400.23  6424.1 1403.45
#Mann= 3 ,-1 , 0
  4058.6     .05       0  4983.1     .05       0  4996.7     .05       0
Bank Sta=4983.1,4996.7
XS Rating Curve= 0 ,0
Exp/Cntr=0.3,0.1

Type RM Length L Ch R = 1 ,2500    ,500,500,500
BEGIN DESCRIPTION:
PONTOTOC CREEK 5.0
END DESCRIPTION:
XS GIS Cut Line= 3
      2729855.69     10292603.12      2728911.15     10291647.84
      2727905.66     10290653.09
#Sta/Elev= 30
  3656.6 1403.09  3812.1 1396.41  3967.7 1387.55  4066.7 1383.87  4102.1  1383.2
  4109.1 1384.17  4116.3 1383.14  4123.3 1384.83  4130.4 1383.29  4151.6 1382.69
  4337.3 1384.07  4411.4 1383.29  4568.8 1382.52  4950.6 1384.27    4986 1381.98
    4993 1379.85  4993.5 1379.35  5006.6 1379.85  5035.5 1383.91  5205.2 1389.14
  5438.6 1390.69  5700.2 1388.25  5787.4 1388.89  5892.1 1390.71  6032.6 1393.62
  6096.2 1396.56  6152.7 1396.59  6301.3 1400.08  6393.2 1402.96  6414.4 1404.89
#Mann= 7 ,-1 , 0
  3656.6     .05       0  4337.3     .12       0  4411.4     .05       0
    4993     .05       0  5006.6     .05       0  5787.4     .12       0
  5892.1     .05       0
Bank Sta=4993,5006.6
XS Rating Curve= 0 ,0
Exp/Cntr=0.3,0.1

Type RM Length L Ch R = 1 ,2000    ,500,500,500
BEGIN DESCRIPTION:
PONTOTOC CREEK 4.0
END DESCRIPTION:
XS GIS Cut Line= 3
      2730005.71     10292253.15      2729353.87       10291442.
       2728655.7     10290453.13
#Sta/Elev= 30
  3959.4 1403.92    4216 1391.72  4286.6 1387.77  4307.5 1385.39  4371.5 1383.96
  4435.5 1380.35  4485.4 1379.46  4499.5 1380.86  4537.5 1380.27  4829.2 1380.45
  4955.4 1381.75  4976.2 1381.18  4984.2 1380.08  4989.2 1377.47  4989.7 1376.97
  5002.9 1377.47  5026.1 1381.02  5055.6 1382.33  5112.2 1382.27  5133.3  1380.9
  5206.7 1379.99  5435.9  1379.6  5483.4 1380.28  5614.6 1382.45  5852.3 1391.26
  5938.4 1393.25  5974.1 1394.87  5980.3 1396.12  6039.1 1396.84  6210.5 1402.97
#Mann= 7 ,-1 , 0
  3959.4     .05       0  4537.5     .12       0  4829.2     .05       0
  4989.2     .05       0  5002.9     .05       0  5435.9     .12       0
  5483.4     .05       0
Bank Sta=4989.2,5002.9
XS Rating Curve= 0 ,0
Exp/Cntr=0.3,0.1

Type RM Length L Ch R = 1 ,1500    ,500,500,500
BEGIN DESCRIPTION:
PONTOTOC CREEK 3.0
END DESCRIPTION:
XS GIS Cut Line= 3
      2730105.68      10292053.1      2729768.79     10291408.64
      2728755.68     10290403.11
#Sta/Elev= 30
  4272.8 1401.38  4391.4 1393.35  4479.7 1389.61    4679 1378.97  4777.5 1378.45
  4904.3 1379.72  4965.9 1378.97  4983.7 1377.53  4985.8 1376.08  4986.3 1375.58
  4999.5 1376.08  5009.3 1377.01  5020.2 1378.04    5098 1380.18  5126.3 1379.68
  5147.5 1380.85    5215 1380.31  5244.9  1379.9  5365.2 1379.59  5380.9 1381.31
  5387.9 1383.14  5430.4 1379.34  5589.3 1379.21  5769.8 1381.39  5911.2 1385.14
  6024.3 1386.68    6187 1392.15  6222.3  1392.4  6271.9 1395.31  6427.4 1400.91
#Mann= 9 ,-1 , 0
  4272.8     .05       0  4965.9     .12       0  4985.8     .07       0
  4999.5     .12       0  5009.3     .05       0    5215     .12       0
  5244.9     .05       0  5365.2     .12       0  5589.3     .05       0
Bank Sta=4985.8,4999.5
XS Rating Curve= 0 ,0
Exp/Cntr=0.3,0.1

Type RM Length L Ch R = 1 ,1000    ,500,500,500
BEGIN DESCRIPTION:
PONTOTOC CREEK 2.0
END DESCRIPTION:
XS GIS Cut Line= 3
      2730255.68     10291953.09      2730206.47     10291288.61
      2729655.69     10290453.12
#Sta/Elev= 30
  4333.7 1393.89  4684.6 1380.07  4724.7 1379.56  4774.9 1377.38  4875.2 1376.82
  4895.2 1373.65  4905.2 1370.83  4925.3 1371.45  4946.6 1370.67  4975.4 1371.61
  4988.2  1369.9  4988.7  1369.4  5002.3  1369.9  5011.5 1371.87  5026.6 1370.95
  5032.6 1373.34  5041.7 1375.52  5062.7 1376.65  5068.7 1378.09  5077.8 1377.89
  5090.4 1376.34  5098.9 1377.23  5104.9 1376.51  5150.1 1376.02  5365.9 1376.41
    5415 1375.77  5568.6  1383.4    5683 1386.07  5863.7 1392.14  6000.7 1395.05
#Mann= 3 ,-1 , 0
  4333.7     .05       0  4988.2     .05       0  5002.3     .05       0
Bank Sta=4988.2,5002.3
XS Rating Curve= 0 ,0
Exp/Cntr=0.3,0.1

Type RM Length L Ch R = 1 ,500     ,0,0,0
BEGIN DESCRIPTION:
PONTOTOC CREEK 1.0
END DESCRIPTION:
XS GIS Cut Line= 3
      2730305.68     10291903.12       2730549.4     10290958.25
      2729855.64     10290553.09
#Sta/Elev= 30
  4024.2 1390.73  4362.2 1377.13  4448.7 1376.55  4478.6 1377.39  4499.3 1376.48
  4509.6 1377.22  4565.6 1375.79  4623.2 1376.81  4926.5 1373.87  4974.3 1371.52
  4984.7 1369.59  4987.8 1367.79  4988.3 1367.29  5002.1 1367.79  5005.2 1369.17
  5027.5 1373.36  5058.1 1373.91  5095.3 1371.99  5116.8 1373.38  5138.3 1372.79
  5234.2    1375  5357.4 1381.01  5453.2 1380.32  5548.6 1381.34  5606.5 1382.63
  5641.2 1384.86  5664.4 1384.39  5736.8 1387.44  5795.5 1388.29  5803.4 1389.47
#Mann= 3 ,-1 , 0
  4024.2     .05       0  4987.8     .05       0  5002.1     .05       0
Bank Sta=4987.8,5002.1
XS Rating Curve= 0 ,0
Exp/Cntr=0.3,0.1
Stream Node=PONTOTOC CREEK  ,Reach-1         , 0 , 0 ,Upstream end
Stream Node=PONTOTOC CREEK  ,Reach-1         , 0 , 1 ,Downstream end

Chan Stop Cuts=-1
Use User Specified Reach Order=0
Composite Channel Slope=5