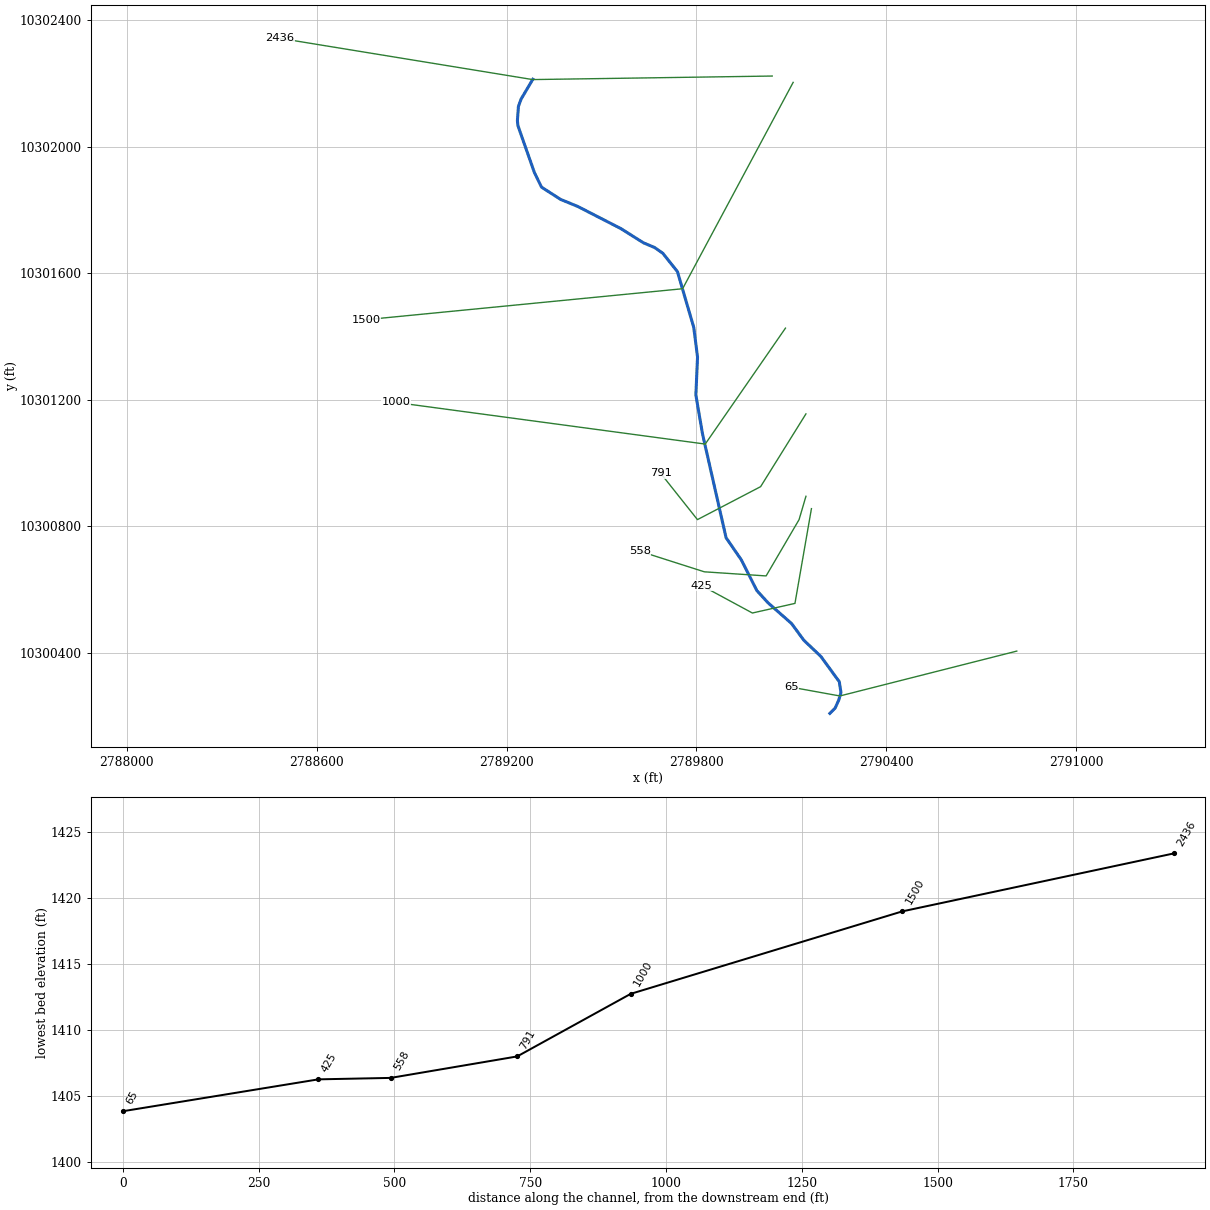
--- RED MT BRANCH.prj (project) ---

Proj Title=RED MT BRANCH Base Level Engineering
Current Plan=p01
Default Exp/Contr=0.3,0.1
English Units
Geom File=g01
Flow File=f01
Plan File=p01
Y Axis Title=Elevation
X Axis Title(PF)=Main Channel Distance
X Axis Title(XS)=Station
BEGIN DESCRIPTION:
RED MT BRANCH
END DESCRIPTION:
DSS Export Rating Curves= 0
DSS Export Rating Curve Sorted= 0
DSS Export Volume Flow Curves= 0
DXF OffsetX= 0
DXF OffsetY= 0
DXF ScaleX= 1
DXF ScaleY= 10

--- RED MT BRANCH.p01 (plan) ---

Plan Title=Multiple Run
Short Identifier=Multiple
Geom File=g01
Flow File=f01
Subcritical Flow
K Sum by GR= 0
Std Step Tol= 0.01
Critical Tol= 0.01
Num of Std Step Trials= 20
Max Error Tol= 0.3
Flow Tol Ratio= 0.001
Split Flow NTrial= 30
Split Flow Tol= 0.02
Split Flow Ratio= 0.02
Log Output Level= 0
Friction Slope Method= 1
Unsteady Friction Slope Method= 2
Unsteady Bridges Friction Slope Method= 1
Parabolic Critical Depth
Global Vel Dist=  1 , 1 , 1
Global Log Level= 0
CheckData=True
Encroach Param= -1, 0, 0, 0
BEGIN DESCRIPTION:
Multiple Run
END DESCRIPTION:

--- RED MT BRANCH.f01 (steady flow) ---

Flow Title=Multiple
Program Version=4.10
Number of Profiles= 7
Profile Names=10-year,25-year,50-year,1pct_min,100-year,1pct_plu,500-year
River Rch & RM=RED MT BRANCH,Reach-1         ,2436
    1152    2007    2577    1581    3538    7915    4842
River Rch & RM=RED MT BRANCH,Reach-1         ,65
    1300    2274    3065    2411    4235    7438    5791
Boundary for River Rch & Prof#=RED MT BRANCH,Reach-1         , 1
Up Type= 0
Dn Type= 3
Dn Slope=0.005
Boundary for River Rch & Prof#=RED MT BRANCH,Reach-1         , 2
Up Type= 0
Dn Type= 3
Dn Slope=0.005
Boundary for River Rch & Prof#=RED MT BRANCH,Reach-1         , 3
Up Type= 0
Dn Type= 3
Dn Slope=0.005
Boundary for River Rch & Prof#=RED MT BRANCH,Reach-1         , 4
Up Type= 0
Dn Type= 3
Dn Slope=0.005
Boundary for River Rch & Prof#=RED MT BRANCH,Reach-1         , 5
Up Type= 0
Dn Type= 3
Dn Slope=0.005
Boundary for River Rch & Prof#=RED MT BRANCH,Reach-1         , 6
Up Type= 0
Dn Type= 3
Dn Slope=0.005
Boundary for River Rch & Prof#=RED MT BRANCH,Reach-1         , 7
Up Type= 0
Dn Type= 3
Dn Slope=0.005
DSS Import GetInterval= 0
DSS Import GetPeak= 0
DSS Import FillOption= 0

--- RED MT BRANCH.g01 (geometry) ---

Geom Title=Existing Conditions
Program Version=4.10

River Reach=RED MT BRANCH   ,Reach-1
Reach XY= 30
        2789283.       10302213.      2789245.75       10302150.
       2789237.5       10302127.      2789234.25       10302082.
        2789236.       10302066.        2789288.       10301918.
       2789310.5       10301872.      2789371.25       10301833.
        2789425.       10301811.      2789561.25       10301741.
      2789632.75       10301696.      2789668.25       10301681.
      2789693.75       10301663.        2789740.       10301605.
       2789791.5       10301429.       2789803.5       10301335.
      2789798.25       10301215.      2789819.25       10301092.
      2789893.75       10300764.        2789942.       10300694.
        2789991.       10300597.      2790026.75       10300558.
       2790100.5       10300493.       2790139.5       10300440.
      2790193.25       10300389.       2790251.5       10300309.
      2790256.75       10300275.      2790249.75       10300251.
       2790238.5       10300226.      2790221.75       10300209.

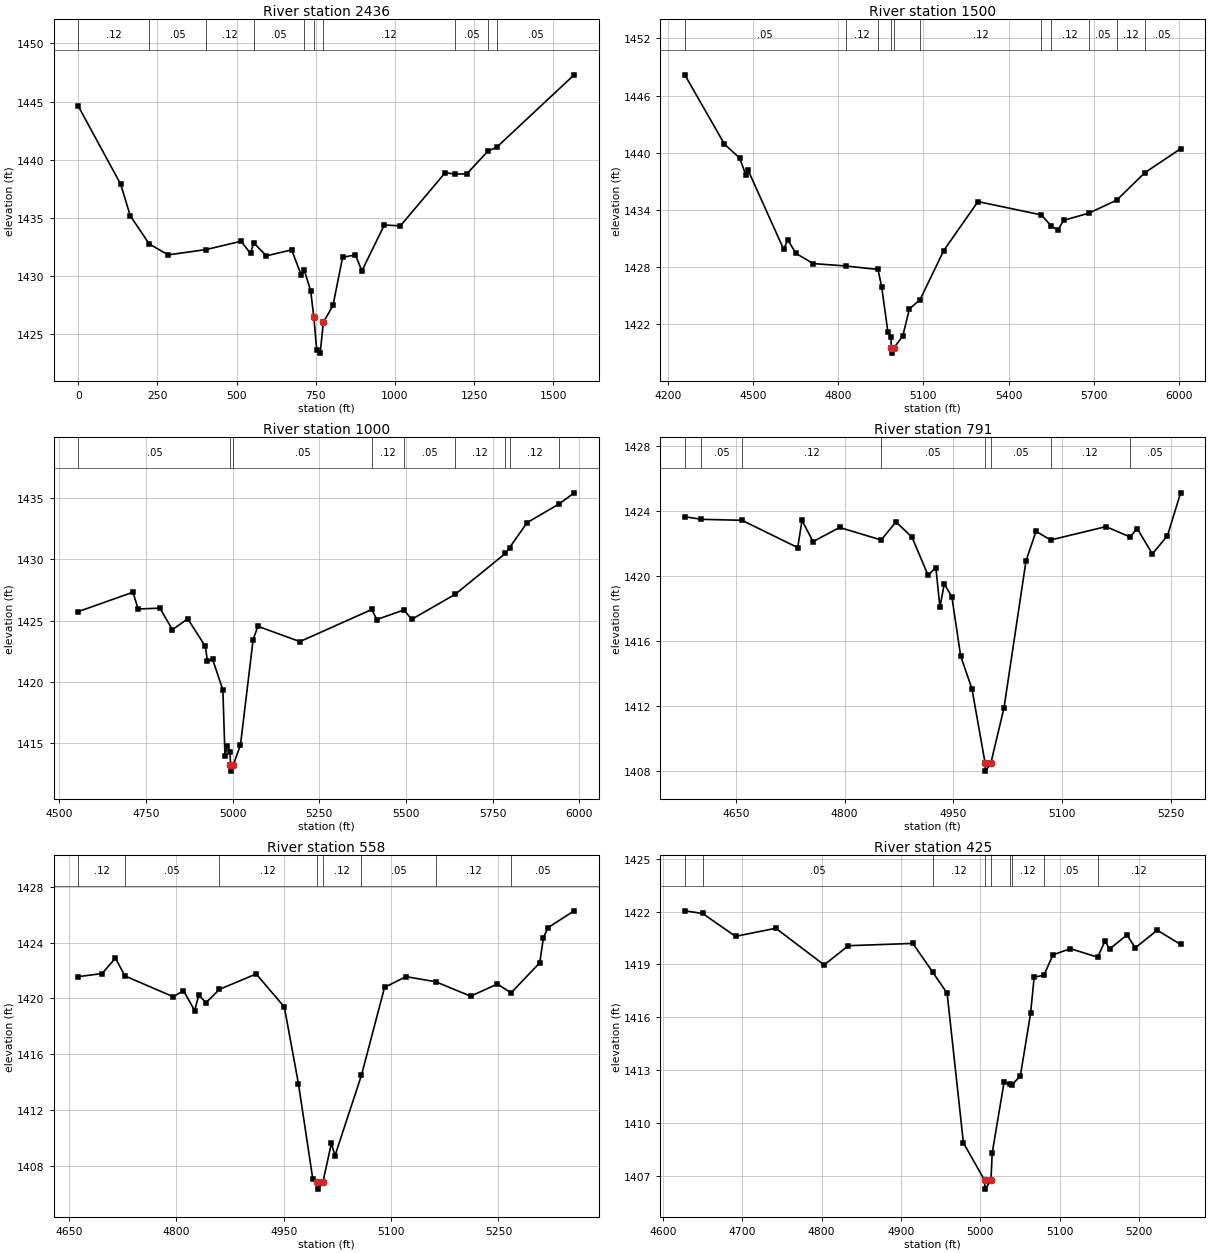
Type RM Length L Ch R = 1 ,2436    ,500,500,500
BEGIN DESCRIPTION:
RED MT BRANCH 4.0
END DESCRIPTION:
XS GIS Cut Line= 3
      2790039.52     10302223.11       2789282.5     10302211.94
      2788483.83     10302342.27
#Sta/Elev= 30
       0  1444.6   133.8  1437.9   163.9  1435.2   223.9 1432.77   283.9 1431.83
   403.9 1432.29   513.9    1433   543.9 1431.96   553.9 1432.87   593.9 1431.75
   673.9 1432.26   703.9 1430.11   713.9  1430.5   733.9 1428.75   743.9 1426.48
     753  1423.7     764 1423.39   774.1 1426.04   804.5 1427.49   834.9 1431.63
   875.5 1431.82   895.7 1430.46   966.7  1434.4  1017.3 1434.32  1159.2  1438.9
  1189.6 1438.76  1227.5  1438.8  1294.1 1440.75  1321.3 1441.07  1566.3  1447.3
#Mann= 10 ,-1 , 0
       0     .12       0   223.9     .05       0   403.9     .12       0
   553.9     .05       0   713.9     .12       0   743.9     .05       0
   774.1     .12       0  1189.6     .05       0  1294.1     .05       0
  1321.3     .05       0
Bank Sta=743.9,774.1
XS Rating Curve= 0 ,0
Exp/Cntr=0.3,0.1

Type RM Length L Ch R = 1 ,1500    ,500,500,500
BEGIN DESCRIPTION:
RED MT BRANCH 3.0
END DESCRIPTION:
XS GIS Cut Line= 3
      2790105.68     10302203.11      2789756.37     10301550.97
      2788755.64     10301453.11
#Sta/Elev= 30
  4260.2 1448.17  4399.9  1440.9  4453.1 1439.45  4475.7 1437.63    4482 1438.24
  4607.9  1429.9  4623.2 1430.84  4651.8 1429.44  4711.9 1428.38  4826.2 1428.13
  4940.3 1427.76  4953.2 1425.94  4975.1 1421.21  4985.7 1420.67  4987.4 1419.49
  4987.9 1418.99  4995.4 1419.49  5027.6 1420.81  5050.9 1423.63  5088.7 1424.61
  5171.5 1429.74  5292.1 1434.88  5515.3 1433.48  5550.9 1432.29  5573.4  1431.9
  5593.5 1432.91  5681.8 1433.66  5780.6 1435.03  5879.5 1437.91  6005.5 1440.42
#Mann= 11 ,-1 , 0
  4260.2     .05       0  4826.2     .12       0  4940.3     .05       0
  4987.4     .05       0  4995.4     .05       0  5088.7     .12       0
  5515.3     .05       0  5550.9     .12       0  5681.8     .05       0
  5780.6     .12       0  5879.5     .05       0
Bank Sta=4987.4,4995.4
XS Rating Curve= 0 ,0
Exp/Cntr=0.3,0.1

Type RM Length L Ch R = 1 ,1000    ,209,209,209
BEGIN DESCRIPTION:
RED MT BRANCH 2.0
END DESCRIPTION:
XS GIS Cut Line= 3
      2790081.33     10301426.42      2789827.85     10301060.07
      2788851.15     10301191.48
#Sta/Elev= 30
  4554.5 1425.75  4712.2 1427.33    4727 1425.96  4789.9 1426.03  4826.1 1424.27
  4870.3 1425.16    4921 1422.91  4927.1 1421.72  4941.9 1421.86  4971.7 1419.35
  4977.7 1413.97  4984.1 1414.79  4992.6 1414.33  4993.5 1413.23    4994 1412.73
  5001.5 1413.23  5022.4 1414.86    5059 1423.47  5072.8 1424.55  5193.9  1423.3
  5401.4 1425.92  5415.9  1425.1    5494 1425.88  5516.8 1425.12  5642.3 1427.16
  5787.2  1430.5  5798.9 1430.96  5849.8 1433.01  5943.1 1434.55  5985.5 1435.44
#Mann= 9 ,-1 , 0
  4554.5     .05       0  4993.5     .05       0  5001.5     .05       0
  5401.4     .12       0    5494     .05       0  5642.3     .12       0
  5787.2     .05       0  5798.9     .12       0  5943.1     .05       0
Bank Sta=4993.5,5001.5
XS Rating Curve= 0 ,0
Exp/Cntr=0.3,0.1

Type RM Length L Ch R = 1 ,791     ,233,233,233
BEGIN DESCRIPTION:
Mapping XS dd7aa958
END DESCRIPTION:
XS GIS Cut Line= 4
      2790146.08     10301155.47      2790002.88     10300925.47
      2789803.22     10300821.31      2789686.33     10300968.51
#Sta/Elev= 30
  4579.4 1423.63  4602.3 1423.47  4658.2 1423.41  4735.2 1421.73  4741.1  1423.4
  4756.4  1422.1    4793 1422.97  4850.3  1422.2  4870.8 1423.31  4892.9 1422.37
    4915 1420.03  4925.8  1420.5  4931.4 1418.07  4937.4  1419.5  4947.9  1418.7
    4960 1415.06  4975.6 1413.04  4993.7 1408.48  4994.2 1407.98  5001.7 1408.48
  5019.8 1411.87  5050.2 1420.92    5064 1422.73  5084.2  1422.2  5160.4 1423.02
  5193.6 1422.39  5203.7  1422.9  5224.5 1421.34  5245.3 1422.46  5263.5  1425.1
#Mann= 8 ,-1 , 0
  4579.4     .12       0  4602.3     .05       0  4658.2     .12       0
  4850.3     .05       0  4993.7     .05       0  5001.7     .05       0
  5084.2     .12       0  5193.6     .05       0
Bank Sta=4993.7,5001.7
XS Rating Curve= 0 ,0
Exp/Cntr=0.3,0.1

Type RM Length L Ch R = 1 ,558     ,133,133,133
BEGIN DESCRIPTION:
Mapping XS fb168069
END DESCRIPTION:
XS GIS Cut Line= 5
       2790146.1     10300895.06      2790124.41     10300821.31
      2790020.24     10300643.36      2789824.93     10300656.38
      2789620.89      10300721.5
#Sta/Elev= 30
  4662.9 1421.56  4696.2 1421.78  4714.7 1422.89    4728 1421.61  4795.6 1420.12
  4809.8 1420.56  4825.5 1419.13  4831.3 1420.26  4841.1 1419.68  4860.2 1420.65
  4911.5 1421.75  4950.8 1419.39  4970.6 1413.88  4990.6 1407.07  4996.7 1406.85
  4997.2 1406.35  5004.7 1406.85  5016.6 1409.63  5021.6 1408.74  5058.6  1414.5
  5090.9 1420.79  5120.9 1421.56  5162.6 1421.19  5211.2 1420.16  5248.6 1421.03
  5267.8  1420.4  5307.8 1422.55    5313 1424.36  5319.4 1425.07  5355.9 1426.27
#Mann= 8 ,-1 , 0
  4662.9     .12       0    4728     .05       0  4860.2     .12       0
  4996.7     .07       0  5004.7     .12       0  5058.6     .05       0
  5162.6     .12       0  5267.8     .05       0
Bank Sta=4996.7,5004.7
XS Rating Curve= 0 ,0
Exp/Cntr=0.3,0.1

Type RM Length L Ch R = 1 ,425     ,360,360,360
BEGIN DESCRIPTION:
Mapping XS 723d6d9d
END DESCRIPTION:
XS GIS Cut Line= 4
      2790163.47     10300856.06      2790111.38     10300556.55
      2789976.84     10300526.17      2789816.24     10300612.98
#Sta/Elev= 30
  4627.7 1422.04  4650.1 1421.89  4691.6 1420.59  4742.3 1421.05  4803.2 1418.97
  4833.7 1420.06  4914.9 1420.19  4939.8 1418.57  4958.1 1417.36  4978.6 1408.87
  5005.3 1406.74  5005.8 1406.24  5013.3 1406.74  5014.9  1408.3  5029.8  1412.3
  5037.5  1412.2  5039.8 1412.17  5050.3 1412.66  5063.3 1416.24  5067.7 1418.28
    5080 1418.38  5091.4 1419.54  5113.3 1419.89  5147.7 1419.41    5157 1420.33
  5162.7 1419.87  5184.6 1420.67  5195.1 1419.94  5222.7 1420.94  5252.2 1420.13
#Mann= 9 ,-1 , 0
  4627.7     .12       0  4650.1     .05       0  4939.8     .12       0
  5005.3     .07       0  5013.3     .12       0  5037.5     .05       0
  5039.8     .12       0    5080     .05       0  5147.7     .12       0
Bank Sta=5005.3,5013.3
XS Rating Curve= 0 ,0
Exp/Cntr=0.3,0.1

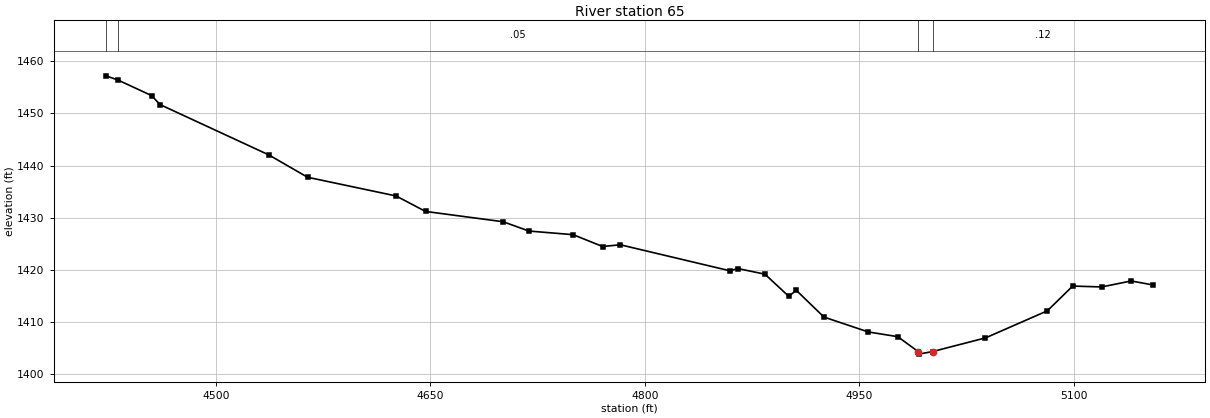
Type RM Length L Ch R = 1 ,65      ,0,0,0
BEGIN DESCRIPTION:
RED MT BRANCH 1.0
END DESCRIPTION:
XS GIS Cut Line= 3
      2790812.35      10300405.8      2790253.25       10300264.
      2790100.34     10300291.71
#Sta/Elev= 30
  4423.2 1457.22  4431.6 1456.42  4455.2 1453.42    4461 1451.71  4537.1 1442.05
  4564.2 1437.76  4626.1 1434.17  4646.7  1431.2    4701 1429.22  4718.9 1427.44
  4749.9 1426.74  4770.5 1424.47  4782.9  1424.8  4859.7  1419.8  4864.9 1420.25
    4884 1419.16  4900.7 1414.91  4905.9 1416.07  4925.3 1410.93  4956.2 1408.08
  4976.9 1407.17  4991.1 1404.32  4991.6 1403.82  5001.3 1404.32  5038.2 1406.93
  5081.5 1412.13  5099.2 1416.88  5119.5 1416.71  5140.1 1417.86  5155.4 1417.09
#Mann= 4 ,-1 , 0
  4423.2     .12       0  4431.6     .05       0  4991.1     .07       0
  5001.3     .12       0
Bank Sta=4991.1,5001.3
XS Rating Curve= 0 ,0
Exp/Cntr=0.3,0.1
Stream Node=RED MT BRANCH   ,Reach-1         , 0 , 0 ,Upstream end
Stream Node=RED MT BRANCH   ,Reach-1         , 0 , 1 ,Downstream end

Chan Stop Cuts=-1
Use User Specified Reach Order=0
Composite Channel Slope=5