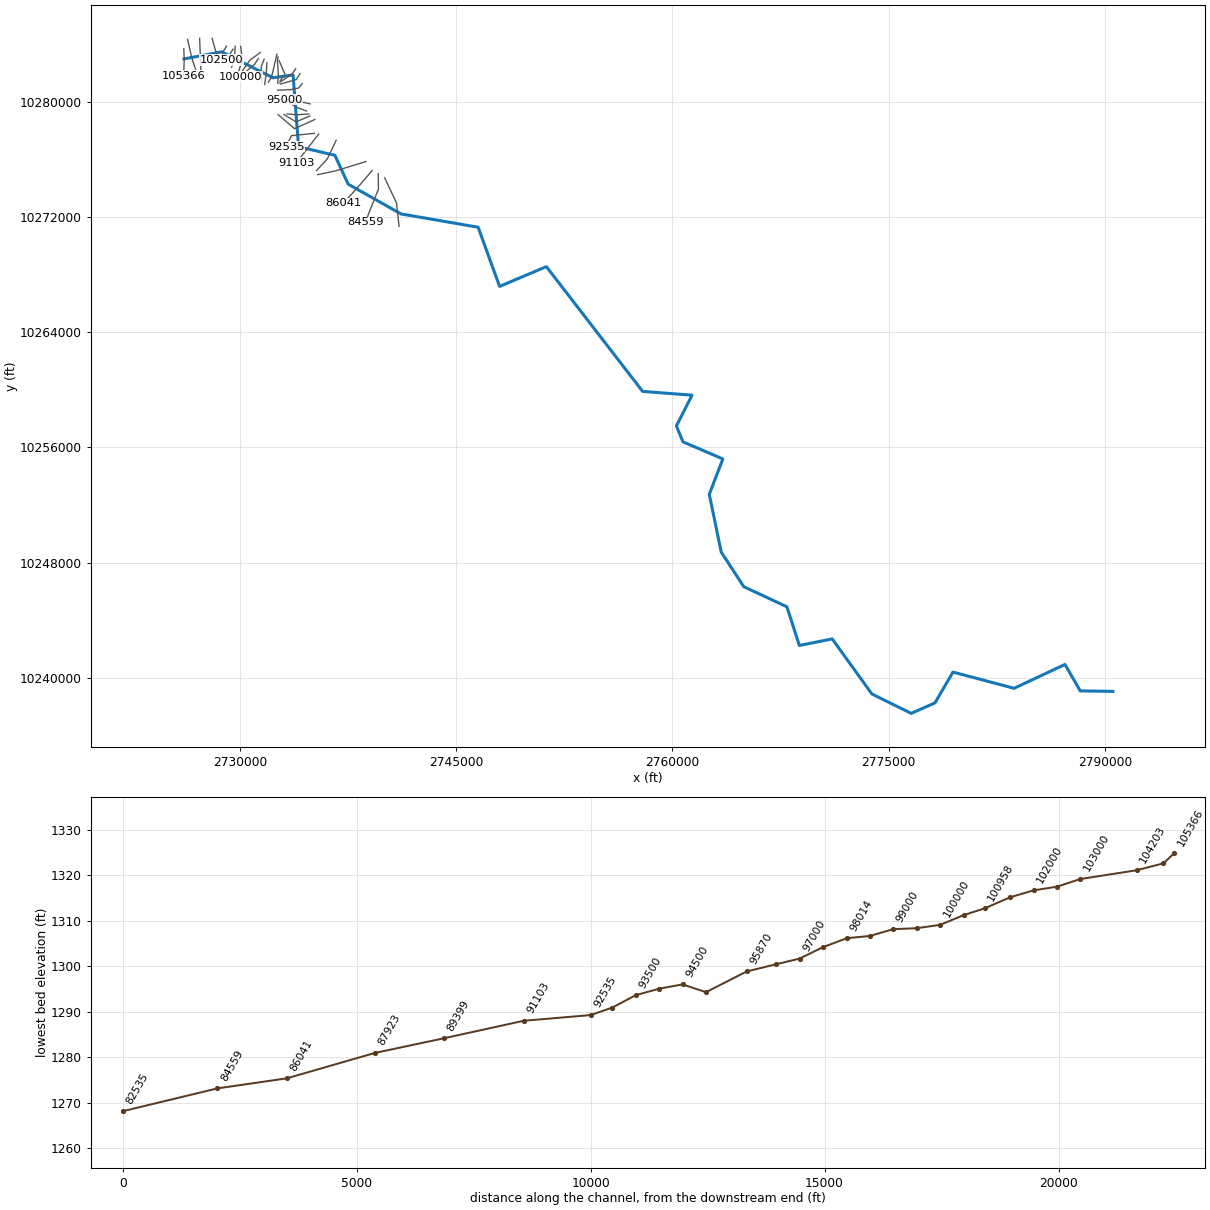
--- SAN FERNANDO CREEK.prj (project) ---

Proj Title=SAN FERNANDO CREEK Base Level Engineering
Current Plan=p01
Default Exp/Contr=0.3,0.1
English Units
Geom File=g01
Flow File=f01
Plan File=p01
Y Axis Title=Elevation
X Axis Title(PF)=Main Channel Distance
X Axis Title(XS)=Station
BEGIN DESCRIPTION:
SAN FERNANDO CREEK
END DESCRIPTION:
DSS Export Rating Curves= 0
DSS Export Rating Curve Sorted= 0
DSS Export Volume Flow Curves= 0
DXF OffsetX= 0
DXF OffsetY= 0
DXF ScaleX= 1
DXF ScaleY= 10

--- SAN FERNANDO CREEK.p01 (plan) ---

Plan Title=Multiple Run
Short Identifier=Multiple
Geom File=g01
Flow File=f01
Subcritical Flow
K Sum by GR= 0
Std Step Tol= 0.01
Critical Tol= 0.01
Num of Std Step Trials= 20
Max Error Tol= 0.3
Flow Tol Ratio= 0.001
Split Flow NTrial= 30
Split Flow Tol= 0.02
Split Flow Ratio= 0.02
Log Output Level= 0
Friction Slope Method= 1
Unsteady Friction Slope Method= 2
Unsteady Bridges Friction Slope Method= 1
Parabolic Critical Depth
Global Vel Dist=  1 , 1 , 1
Global Log Level= 0
CheckData=True
Encroach Param= -1, 0, 0, 0
BEGIN DESCRIPTION:
Multiple Run
END DESCRIPTION:

--- SAN FERNANDO CREEK.f01 (steady flow) ---

Flow Title=Multiple
Program Version=4.10
Number of Profiles= 7
Profile Names=10-year,25-year,50-year,1pct_min,100-year,1pct_plu,500-year
River Rch & RM=SAN FERNANDO CRE,Reach-1         ,105366
    7169   13610   22186   29083   31945   35089   42430
River Rch & RM=SAN FERNANDO CRE,Reach-1         ,100000
    7298   13859   22433   16652   32288   62606   42829
River Rch & RM=SAN FERNANDO CRE,Reach-1         ,94500
   13010   24358   38026   34589   53941   84121   70108
River Rch & RM=SAN FERNANDO CRE,Reach-1         ,92535
   12982   24261   37642   29293   53320   97051   69166
River Rch & RM=SAN FERNANDO CRE,Reach-1         ,86041
   12641   23616   36552   28405   51762   94327   67114
River Rch & RM=SAN FERNANDO CRE,Reach-1         ,82535
   13432   25030   38536   30164   54457   98314   70437
River Rch & RM=SAN FERNANDO CRE,Reach-1         ,80840
   19787   36323   54357   41984   75884  137157   96898
River Rch & RM=SAN FERNANDO CRE,Reach-1         ,77727
   19991   36651   54712   46779   76303  124461   97337
River Rch & RM=SAN FERNANDO CRE,Reach-1         ,75639
   18983   34769   51770   44367   72146  117316   91960
River Rch & RM=SAN FERNANDO CRE,Reach-1         ,69126
   18441   33767   50239   42104   69998  116373   89204
River Rch & RM=SAN FERNANDO CRE,Reach-1         ,68000
   18297   33493   49796   42079   69364  114341   88372
River Rch & RM=SAN FERNANDO CRE,Reach-1         ,67000
   21123   38459   56654   47245   78579  130695   99703
River Rch & RM=SAN FERNANDO CRE,Reach-1         ,62005
   20558   37422   55094   43095   76400  135444   96921
River Rch & RM=SAN FERNANDO CRE,Reach-1         ,59998
   21071   38333   56382   44467   78151  137351   99099
River Rch & RM=SAN FERNANDO CRE,Reach-1         ,58239
   20504   37297   54837   41849   76002  138025   96365
River Rch & RM=SAN FERNANDO CRE,Reach-1         ,54768
   21093   38281   56108   43215   77642  139494   98298
River Rch & RM=SAN FERNANDO CRE,Reach-1         ,51338
   20346   36890   54017   41738   74714  133745   94547
River Rch & RM=SAN FERNANDO CRE,Reach-1         ,45206
   19402   35176   51490   40150   71214  126315   90113
River Rch & RM=SAN FERNANDO CRE,Reach-1         ,40945
   21596   38953   56789   44555   78342  137751   98879
River Rch & RM=SAN FERNANDO CRE,Reach-1         ,36500
   21332   38474   56083   44238   77366  135303   97644
River Rch & RM=SAN FERNANDO CRE,Reach-1         ,35000
   21204   38206   55643   43939   76722  133963   96783
River Rch & RM=SAN FERNANDO CRE,Reach-1         ,29742
   21395   38517   56056   44239   77258  134920   97417
River Rch & RM=SAN FERNANDO CRE,Reach-1         ,26063
   21614   38877   56537   44619   77886  135955   98166
River Rch & RM=SAN FERNANDO CRE,Reach-1         ,22981
   21766   39137   56902   43895   78376  139945   98768
River Rch & RM=SAN FERNANDO CRE,Reach-1         ,21201
   20676   37167   54010   39801   74382  139008   93721
River Rch & RM=SAN FERNANDO CRE,Reach-1         ,15983
   20165   36240   52647   38963   72497  134891   91336
River Rch & RM=SAN FERNANDO CRE,Reach-1         ,12222
   19668   35320   51271   37535   70576  132703   88884
River Rch & RM=SAN FERNANDO CRE,Reach-1         ,5770
   19474   34962   50735   37999   69828  128318   87928
River Rch & RM=SAN FERNANDO CRE,Reach-1         ,3553
   19557   35106   50938   38147   70103  128829   88268
Boundary for River Rch & Prof#=SAN FERNANDO CRE,Reach-1         , 1
Up Type= 0
Dn Type= 3
Dn Slope=0.001
Boundary for River Rch & Prof#=SAN FERNANDO CRE,Reach-1         , 2
Up Type= 0
Dn Type= 3
Dn Slope=0.001
Boundary for River Rch & Prof#=SAN FERNANDO CRE,Reach-1         , 3
Up Type= 0
Dn Type= 3
Dn Slope=0.001
Boundary for River Rch & Prof#=SAN FERNANDO CRE,Reach-1         , 4
Up Type= 0
Dn Type= 3
Dn Slope=0.001
Boundary for River Rch & Prof#=SAN FERNANDO CRE,Reach-1         , 5
Up Type= 0
Dn Type= 3
Dn Slope=0.001
Boundary for River Rch & Prof#=SAN FERNANDO CRE,Reach-1         , 6
Up Type= 0
Dn Type= 3
Dn Slope=0.001
Boundary for River Rch & Prof#=SAN FERNANDO CRE,Reach-1         , 7
Up Type= 0
Dn Type= 3
Dn Slope=0.001
DSS Import GetInterval= 0
DSS Import GetPeak= 0
DSS Import FillOption= 0

--- SAN FERNANDO CREEK.g01 (geometry) ---

Geom Title=Existing Conditions
Program Version=4.10

River Reach=SAN FERNANDO CRE,Reach-1
Reach XY= 30
        2726100.       10282974.      2728716.25       10283470.
      2732284.25       10281665.       2733673.5       10281866.
      2734052.75       10276878.      2736572.75       10276283.
       2737495.5       10274279.        2741160.       10272211.
       2746512.5       10271286.      2748003.25       10267178.
        2751251.       10268548.        2757928.       10259884.
      2761355.75       10259621.      2760271.75       10257485.
        2760727.       10256380.        2763495.       10255192.
      2762552.75       10252735.      2763381.25       10248724.
      2764946.25       10246320.       2767938.5       10244924.
        2768804.       10242238.        2771083.       10242693.
      2773836.75       10238867.       2776566.5       10237521.
       2778214.5       10238252.      2779462.25       10240389.
      2783701.75       10239263.        2787236.       10240919.
      2788293.25       10239082.      2790561.25       10239049.

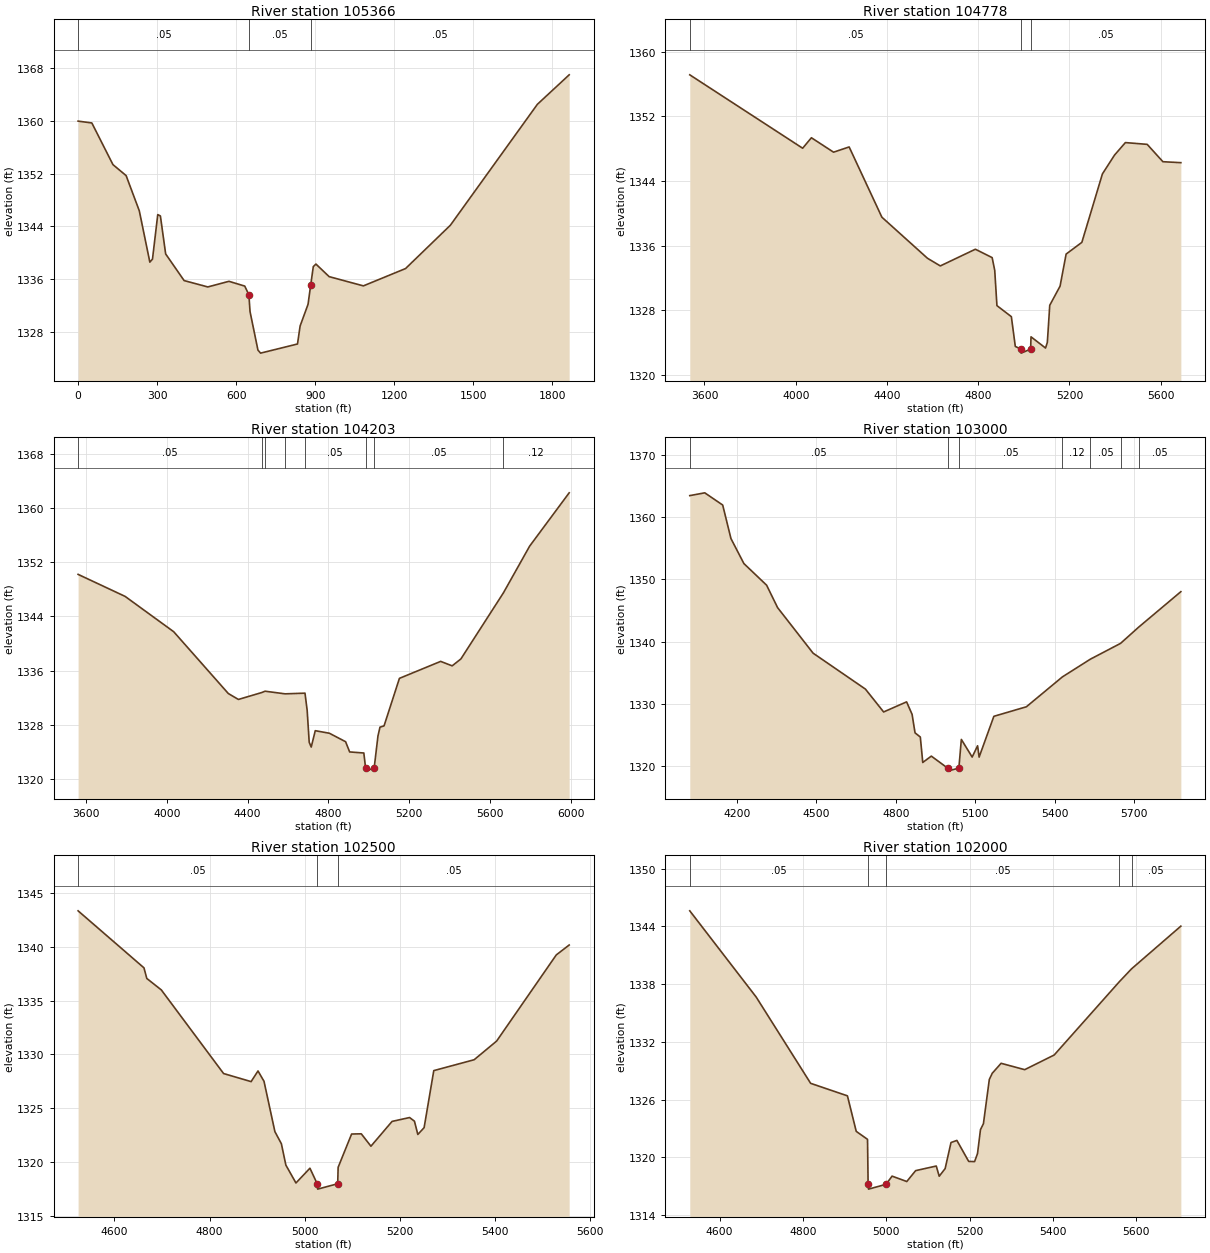
Type RM Length L Ch R = 1 ,105366  ,222,222,222
BEGIN DESCRIPTION:
SAN FERNANDO CREEK 210.0
END DESCRIPTION:
XS GIS Cut Line= 3
      2726090.51     10283685.29      2726119.78     10282920.69
      2726080.46     10281822.43
#Sta/Elev= 30
       0 1359.93    52.2 1359.65   132.3 1353.35   182.3 1351.69   232.3 1346.37
   272.4  1338.6   282.4 1339.06   302.4 1345.79   312.4 1345.59   332.4 1339.84
   402.5 1335.81   492.5 1334.85   572.6  1335.7   632.6 1334.98  648.31 1333.65
   652.7 1331.11   682.7  1325.3   692.7 1324.84   832.8 1326.22   842.8 1328.95
   872.8 1332.21   882.8 1335.09   892.8 1337.92   902.8 1338.31   952.9 1336.41
  1082.9 1335.01    1243 1337.63  1413.1 1344.18  1743.4 1362.47  1864.1 1366.93
#Mann= 3 , 0 , 0
       0     .05       0  648.31     .05       0   882.8     .05       0
Bank Sta=648.31,882.8
XS Rating Curve= 0 ,0
Exp/Cntr=0.3,0.1

Type RM Length L Ch R = 1 ,104778  ,575,575,575
BEGIN DESCRIPTION:
Mapping XS c3b75512
END DESCRIPTION:
XS GIS Cut Line= 3
      2726353.88       10284335.      2726628.12     10283105.31
      2726906.44      10282257.1
#Sta/Elev= 30
  3535.6 1357.16  4030.4 1348.06  4068.7 1349.36  4165.9 1347.57  4234.2 1348.22
  4377.7 1339.51  4577.5 1334.42  4633.8 1333.47  4787.5 1335.54    4861  1334.5
  4872.3 1332.93    4882 1328.55  4945.2 1327.18  4962.5 1323.49    4987 1323.16
    4988 1322.66  5029.7 1323.16  5031.4 1324.68  5095.1 1323.29    5103    1324
  5113.5 1328.59  5158.7 1330.96  5185.3 1334.94  5254.2 1336.39  5344.4 1344.88
  5397.7 1347.22  5445.1 1348.76  5540.6 1348.54  5609.5 1346.39  5688.2 1346.27
#Mann= 3 ,-1 , 0
  3535.6     .05       0    4987     .03       0  5029.7     .05       0
Bank Sta=4987,5029.7
XS Rating Curve= 0 ,0
Exp/Cntr=0.3,0.1

Type RM Length L Ch R = 1 ,104203  ,1203,1203,1203
BEGIN DESCRIPTION:
Mapping XS ead5ee6c
END DESCRIPTION:
XS GIS Cut Line= 2
      2727189.87     10284405.76      2727282.75     10281977.73
#Sta/Elev= 30
  3561.5 1350.23  3794.3 1346.97  4034.5 1341.75  4304.7 1332.61  4354.7 1331.73
  4469.9 1332.75  4486.5 1332.95  4586.1 1332.56  4684.2 1332.66    4695 1330.09
    4705  1325.4    4715 1324.69    4735 1327.11  4805.1 1326.73  4885.1 1325.48
  4905.1 1323.97  4975.2 1323.81  4983.9 1321.63  4984.9 1321.13  5026.6 1321.63
  5045.2 1326.33  5055.2 1327.63  5075.3 1327.82  5151.4 1334.85  5355.5 1337.36
  5412.3  1336.7  5455.5 1337.72  5665.6 1347.48  5795.8 1354.41  5991.3 1362.29
#Mann= 8 ,-1 , 0
  3561.5     .05       0  4469.9     .12       0  4486.5     .05       0
  4586.1     .12       0  4684.2     .05       0  4983.9     .03       0
  5026.6     .05       0  5665.6     .12       0
Bank Sta=4983.9,5026.6
XS Rating Curve= 0 ,0
Exp/Cntr=0.3,0.1

Type RM Length L Ch R = 1 ,103000  ,500,500,500
BEGIN DESCRIPTION:
SAN FERNANDO CREEK 206.0
END DESCRIPTION:
XS GIS Cut Line= 3
      2728055.69     10284403.07      2728315.65     10283459.73
      2728505.67     10282603.16
#Sta/Elev= 30
  4021.5 1363.43  4078.2 1363.88  4145.9 1361.92  4177.1 1356.54  4226.1 1352.52
  4311.9 1349.05  4353.4 1345.45  4487.5 1338.14  4685.3 1332.37  4754.1  1328.7
  4840.9 1330.32  4861.7 1328.31  4872.8 1325.35  4892.8 1324.67    4902 1320.59
  4934.3 1321.61  4995.6  1319.7  4996.6  1319.2  5038.5  1319.7  5047.8 1324.29
  5088.7 1321.46  5109.2 1323.27    5115 1321.45  5170.7    1328  5293.6 1329.53
  5429.8 1334.33  5535.3 1337.17  5649.5 1339.71  5718.1 1342.32  5877.4 1348.01
#Mann= 7 ,-1 , 0
  4021.5     .05       0  4995.6     .05       0  5038.5     .05       0
  5429.8     .12       0  5535.3     .05       0  5649.5     .12       0
  5718.1     .05       0
Bank Sta=4995.6,5038.5
XS Rating Curve= 0 ,0
Exp/Cntr=0.3,0.1

Type RM Length L Ch R = 1 ,102500  ,500,500,500
BEGIN DESCRIPTION:
SAN FERNANDO CREEK 205.0
END DESCRIPTION:
XS GIS Cut Line= 3
      2729055.69     10283853.11      2728802.37       10283450.
      2728705.68     10282903.08
#Sta/Elev= 30
  4523.9 1343.32  4662.3 1338.03  4668.2 1337.05  4698.8 1335.98  4829.5 1328.23
  4887.3 1327.48  4901.8 1328.47  4914.4 1327.51  4937.3 1322.84  4950.9 1321.72
  4960.3 1319.74  4981.5 1318.08  5010.9 1319.45  5026.1 1318.01  5027.1 1317.51
  5069.2 1318.01  5070.1 1319.53  5098.4 1322.62  5118.7 1322.64    5139 1321.49
  5183.4 1323.79  5220.2 1324.15  5230.4 1323.81  5237.5 1322.58  5250.7 1323.21
    5271  1328.5  5355.8 1329.51    5403 1331.24  5528.3 1339.23  5555.4 1340.15
#Mann= 3 ,-1 , 0
  4523.9     .05       0  5026.1     .03       0  5069.2     .05       0
Bank Sta=5026.1,5069.2
XS Rating Curve= 0 ,0
Exp/Cntr=0.3,0.1

Type RM Length L Ch R = 1 ,102000  ,500,500,500
BEGIN DESCRIPTION:
SAN FERNANDO CREEK 204.0
END DESCRIPTION:
XS GIS Cut Line= 3
      2729505.69     10283653.12      2729253.93     10283254.46
       2728755.7     10282753.13
#Sta/Elev= 30
  4528.5 1345.61  4687.9 1336.65  4818.5 1327.69  4906.8 1326.39  4927.9  1322.7
    4955 1321.87  4956.4  1317.2  4957.4  1316.7  4999.5  1317.2  5013.9 1318.05
  5049.2 1317.49  5070.4 1318.62  5119.9  1319.1    5127 1318.04  5141.2 1318.83
  5155.3 1321.54  5169.4 1321.76  5197.7 1319.58  5211.9 1319.56  5218.9 1320.39
    5226 1322.88  5233.1  1323.5  5247.2 1328.09  5254.3 1328.74  5275.5 1329.77
  5332.1 1329.11  5402.8 1330.63  5559.3 1338.25  5588.4 1339.58  5706.8 1344.02
#Mann= 5 ,-1 , 0
  4528.5     .05       0  4956.4     .05       0  4999.5     .05       0
  5559.3     .12       0  5588.4     .05       0
Bank Sta=4956.4,4999.5
XS Rating Curve= 0 ,0
Exp/Cntr=0.3,0.1

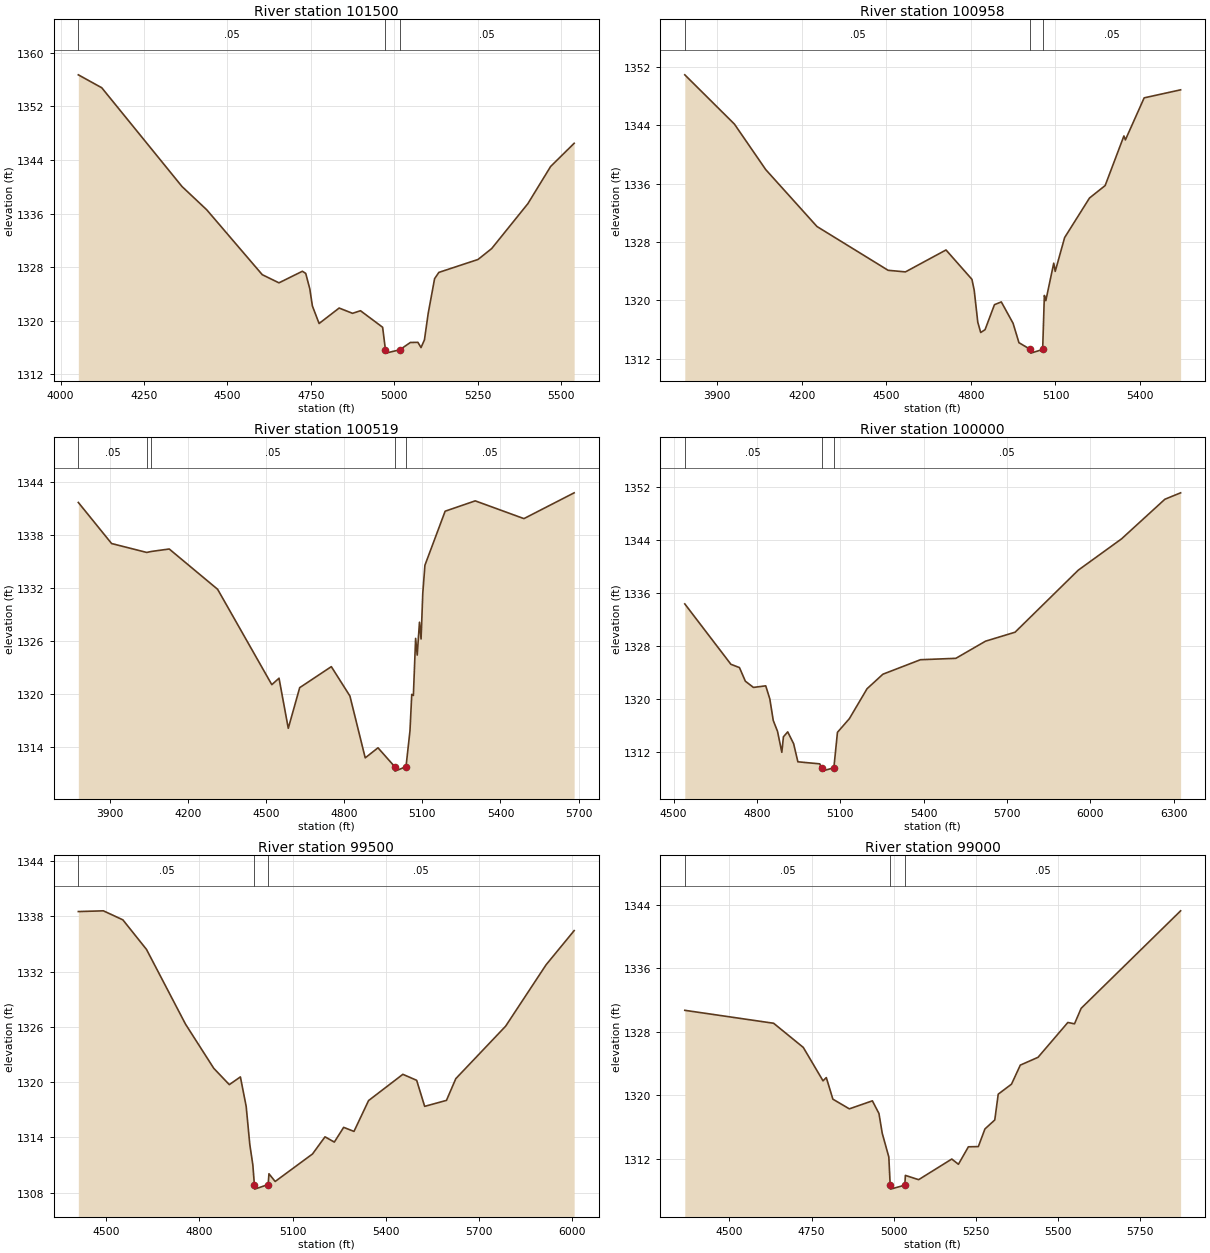
Type RM Length L Ch R = 1 ,101500  ,542,542,542
BEGIN DESCRIPTION:
SAN FERNANDO CREEK 203.0
END DESCRIPTION:
XS GIS Cut Line= 3
      2729655.69     10283853.15      2729594.02     10282908.36
      2729405.69     10282403.12
#Sta/Elev= 30
  4053.2 1356.72  4123.4 1354.79  4363.9 1340.05  4438.1 1336.57  4604.4 1326.89
  4654.5 1325.67  4724.7  1327.4  4734.7 1327.08  4746.9 1324.78  4754.7 1322.22
  4774.8  1319.6  4834.9 1321.91    4875 1321.12  4898.8 1321.51  4965.2 1319.04
  4973.6 1315.68  4974.6 1315.18  5016.7 1315.68  5048.3 1316.77  5070.9 1316.79
  5080.3 1316.01  5090.5 1317.16  5101.7 1321.09  5120.9 1326.29  5133.7 1327.23
  5251.1 1329.16  5292.1 1330.79  5400.5 1337.49  5468.7 1343.04  5539.2  1346.5
#Mann= 3 ,-1 , 0
  4053.2     .05       0  4973.6     .03       0  5016.7     .05       0
Bank Sta=4973.6,5016.7
XS Rating Curve= 0 ,0
Exp/Cntr=0.3,0.1

Type RM Length L Ch R = 1 ,100958  ,439,439,439
BEGIN DESCRIPTION:
Mapping XS c7a064e2
END DESCRIPTION:
XS GIS Cut Line= 3
      2730034.65      10283837.5        2730154.     10282969.46
      2729904.43     10282123.09
#Sta/Elev= 30
  3785.2 1350.95  3961.2 1344.19  4072.3 1337.94    4254 1330.13  4506.3 1324.12
  4567.8  1323.9  4711.7 1326.91  4803.6 1322.88  4811.7 1321.38  4824.4 1316.99
  4834.8 1315.58  4850.2 1315.97  4883.5  1319.4  4907.8 1319.78  4949.5 1316.85
  4970.4 1314.18  5011.3 1313.25  5012.3 1312.75  5054.5 1313.25  5060.5 1320.67
  5065.7 1319.95  5093.8  1325.1    5099 1323.97  5132.4 1328.61  5220.6 1334.04
  5276.1 1335.75  5342.7 1342.56  5347.9 1342.02  5414.5 1347.79  5543.8 1348.89
#Mann= 3 ,-1 , 0
  3785.2     .05       0  5011.3     .05       0  5054.5     .05       0
Bank Sta=5011.3,5054.5
XS Rating Curve= 0 ,0
Exp/Cntr=0.3,0.1

Type RM Length L Ch R = 1 ,100519  ,519,519,519
BEGIN DESCRIPTION:
Mapping XS 7415ddb6
END DESCRIPTION:
XS GIS Cut Line= 3
      2731401.84     10283425.19      2730685.68      10282893.5
      2730100.19     10282069.48
#Sta/Elev= 30
  3779.9 1341.71  3907.5 1337.06  4042.4 1336.05  4059.9 1336.16  4128.7 1336.44
  4314.4 1331.88  4522.4 1321.08  4550.1 1321.81  4585.6 1316.14  4629.4 1320.74
  4750.8 1323.12  4822.1  1319.8  4880.9 1312.79  4929.9 1313.93  4994.2 1311.79
  4995.2 1311.29  5037.4 1311.79  5052.6 1315.84  5059.5 1319.98  5065.7 1319.86
  5074.3 1326.32  5080.4 1324.43  5089.1 1328.15  5095.2 1326.25  5101.7 1331.39
    5110  1334.6  5187.6 1340.72  5303.1 1341.89    5490 1339.88  5682.7  1342.8
#Mann= 5 ,-1 , 0
  3779.9     .05       0  4042.4     .12       0  4059.9     .05       0
  4994.2     .03       0  5037.4     .05       0
Bank Sta=4994.2,5037.4
XS Rating Curve= 0 ,0
Exp/Cntr=0.3,0.1

Type RM Length L Ch R = 1 ,100000  ,500,500,500
BEGIN DESCRIPTION:
SAN FERNANDO CREEK 200.0
END DESCRIPTION:
XS GIS Cut Line= 3
      2731255.66     10283003.07       2731013.4     10282612.26
      2730005.65     10281753.08
#Sta/Elev= 30
  4540.2 1334.39  4706.1 1325.26  4736.9 1324.76  4758.1  1322.7  4787.2 1321.76
  4831.4    1322  4846.1 1320.03  4858.5 1316.76  4873.9 1315.11  4889.3 1311.95
  4895.1 1314.29  4910.5 1315.04  4931.8 1313.25  4947.1 1310.51  5025.8  1310.2
  5032.2  1309.6  5033.2  1309.1  5076.6  1309.6  5089.5 1314.97  5132.3 1317.03
    5196 1321.56  5253.1 1323.76  5388.2 1325.95  5515.6 1326.16  5622.1 1328.75
  5728.6 1330.11  5955.9 1339.49  6111.8 1344.23  6267.7 1350.22  6324.3 1351.19
#Mann= 3 ,-1 , 0
  4540.2     .05       0  5032.2     .03       0  5076.6     .05       0
Bank Sta=5032.2,5076.6
XS Rating Curve= 0 ,0
Exp/Cntr=0.3,0.1

Type RM Length L Ch R = 1 ,99500   ,500,500,500
BEGIN DESCRIPTION:
SAN FERNANDO CREEK 199.0
END DESCRIPTION:
XS GIS Cut Line= 3
      2731662.23     10282958.56       2731456.1     10282407.24
      2731505.69     10281403.06
#Sta/Elev= 30
  4411.4 1338.52    4492  1338.6  4554.6 1337.62  4630.7  1334.4    4756 1326.29
  4846.9 1321.49  4896.8 1319.72  4932.4 1320.56    4951 1317.36  4962.7 1313.21
  4972.4 1311.01  4977.3 1308.87  4978.3 1308.37  5021.8 1308.87  5024.2 1310.04
  5044.2  1309.2  5164.3 1312.19  5204.4 1314.05  5234.4 1313.48  5264.4 1315.08
  5297.6 1314.64  5344.5 1317.99  5454.7 1320.84  5499.1 1320.19  5524.8 1317.36
  5594.9 1318.01  5624.9 1320.37  5785.1 1326.07  5915.2 1332.74  6005.4 1336.45
#Mann= 3 ,-1 , 0
  4411.4     .05       0  4977.3     .05       0  5021.8     .05       0
Bank Sta=4977.3,5021.8
XS Rating Curve= 0 ,0
Exp/Cntr=0.3,0.1

Type RM Length L Ch R = 1 ,99000   ,500,500,500
BEGIN DESCRIPTION:
SAN FERNANDO CREEK 198.0
END DESCRIPTION:
XS GIS Cut Line= 3
      2731855.68     10282703.09      2731822.42     10282068.36
      2731705.68      10281203.1
#Sta/Elev= 30
  4364.4 1330.68  4634.7 1329.05  4724.9 1326.01    4785  1321.8    4795 1322.21
    4815 1319.49  4865.1 1318.27  4935.2 1319.28  4955.2 1317.68  4965.2 1315.19
  4985.2 1312.21  4989.4 1308.66  4990.4 1308.16  5033.9 1308.66  5035.6 1309.89
  5075.9 1309.35  5176.8 1311.95    5197 1311.29  5227.3 1313.49  5257.6 1313.52
  5277.7 1315.74  5307.6 1316.87  5318.1 1320.12  5358.5 1321.38  5385.3 1323.78
  5439.2 1324.76    5530 1329.15  5550.2 1328.98  5570.4 1330.93  5873.1 1343.21
#Mann= 3 ,-1 , 0
  4364.4     .05       0  4989.4     .05       0  5033.9     .05       0
Bank Sta=4989.4,5033.9
XS Rating Curve= 0 ,0
Exp/Cntr=0.3,0.1

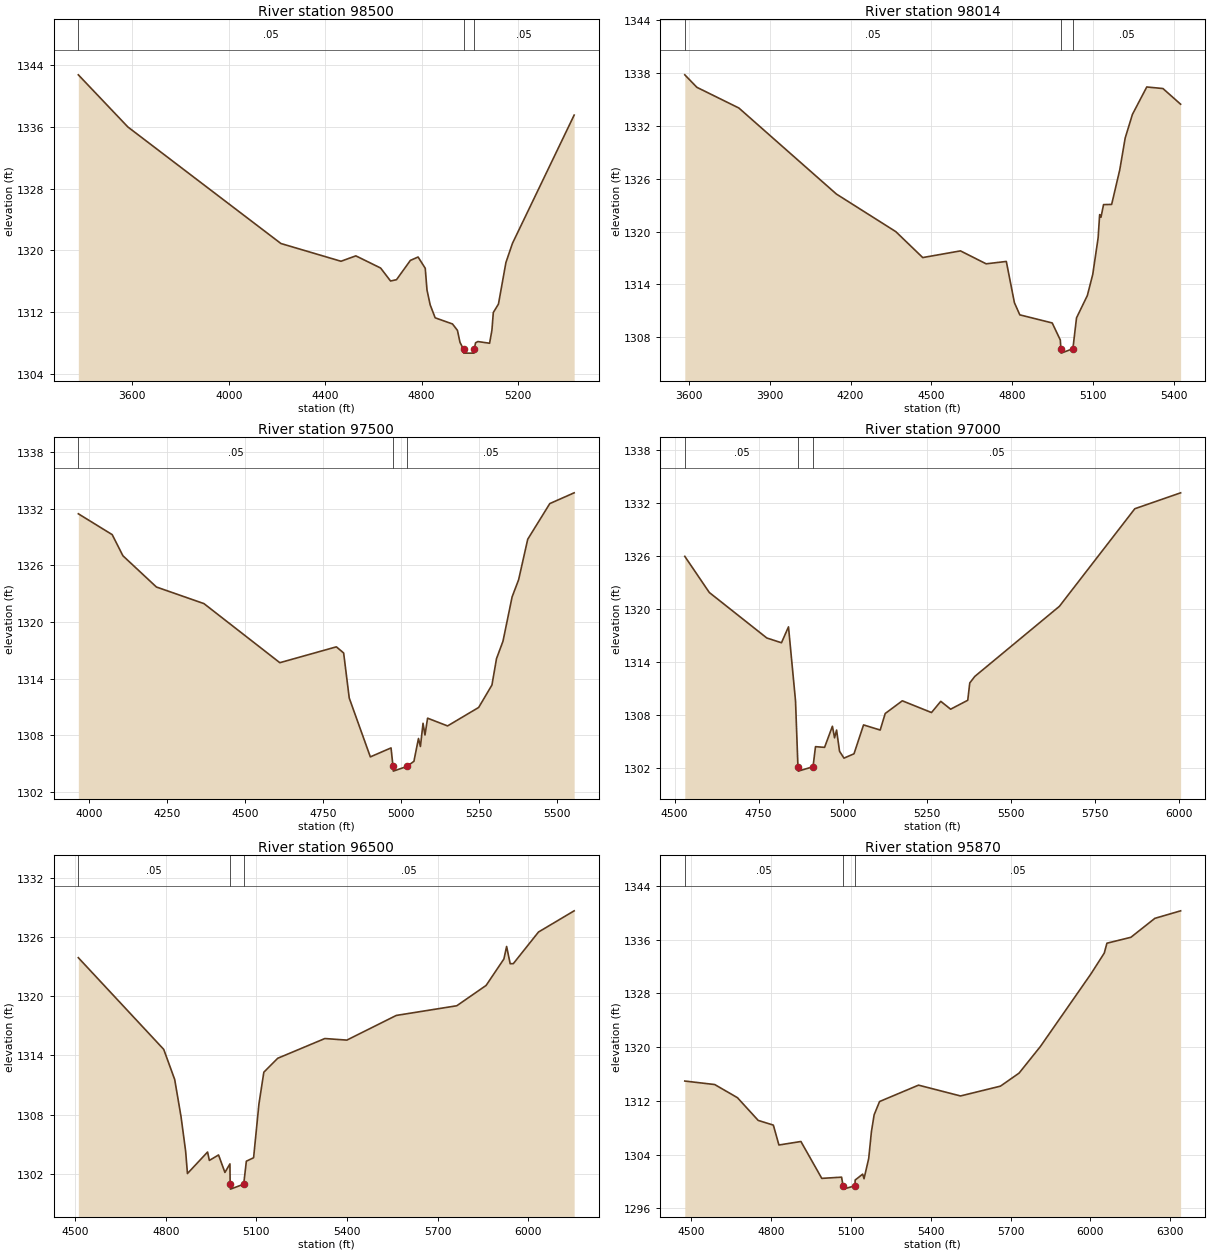
Type RM Length L Ch R = 1 ,98500   ,486,486,486
BEGIN DESCRIPTION:
SAN FERNANDO CREEK 197.0
END DESCRIPTION:
XS GIS Cut Line= 3
      2732555.68     10283303.09      2732180.05     10281722.92
      2731955.71     10281353.15
#Sta/Elev= 30
  3375.8 1342.74  3581.3 1335.98  4216.2 1320.87  4465.3 1318.57    4527 1319.27
  4629.8 1317.69  4670.9 1316.01  4695.6 1316.18  4753.1 1318.68  4785.1 1319.12
  4814.8 1317.66  4822.1 1314.84  4835.3 1312.92  4855.9 1311.24  4927.9 1310.44
  4948.4 1309.61  4958.9 1308.06  4973.7 1307.16  4974.7 1306.66  5017.3 1306.66
  5018.3 1307.16  5023.5    1308  5033.2 1308.16  5081.7 1307.94  5091.3 1309.62
  5097.2 1311.93  5118.5 1313.02  5149.5 1318.41  5176.7  1320.9  5432.5 1337.52
#Mann= 3 ,-1 , 0
  3375.8     .05       0  4973.7     .03       0  5018.3     .05       0
Bank Sta=4973.7,5018.3
XS Rating Curve= 0 ,0
Exp/Cntr=0.3,0.1

Type RM Length L Ch R = 1 ,98014   ,514,514,514
BEGIN DESCRIPTION:
Mapping XS f91f6791
END DESCRIPTION:
XS GIS Cut Line= 5
      2732627.95     10283121.33      2732584.56      10282850.1
      2732617.11     10282502.88      2732649.66     10281819.29
      2732606.28     10281287.84
#Sta/Elev= 30
  3584.6 1337.81  3629.5 1336.39  3785.3 1334.04  4147.5 1324.26    4368 1319.99
  4468.1 1317.04  4608.2  1317.8  4703.5 1316.33  4778.4  1316.6  4808.5 1311.91
  4828.5 1310.53  4948.8 1309.61  4978.9 1307.67    4981 1306.68    4982 1306.18
  5025.6 1306.68  5039.1 1310.19  5079.2 1312.72  5099.3 1315.12  5119.3 1319.28
    5125 1321.92    5130 1321.63  5139.4 1323.06  5169.5 1323.08  5199.6 1327.01
  5219.7 1330.62  5246.6 1333.31  5299.9 1336.43  5360.1 1336.25  5425.6 1334.47
#Mann= 3 ,-1 , 0
  3584.6     .05       0    4981     .03       0  5025.6     .05       0
Bank Sta=4981,5025.6
XS Rating Curve= 0 ,0
Exp/Cntr=0.3,0.1

Type RM Length L Ch R = 1 ,97500   ,500,500,500
BEGIN DESCRIPTION:
SAN FERNANDO CREEK 195.0
END DESCRIPTION:
XS GIS Cut Line= 3
      2732705.68     10282853.11      2733114.74     10281903.47
      2732782.37     10281457.75
#Sta/Elev= 30
    3966 1331.47  4074.6 1329.26    4109 1327.02  4216.4 1323.71  4368.9 1321.95
  4612.2 1315.69  4793.5 1317.37  4816.8 1316.72  4834.8 1311.94  4902.4 1305.71
  4968.8 1306.66  4975.1  1304.7  4976.1  1304.2  5019.8  1304.7  5042.2 1305.24
  5056.8 1307.66    5063 1306.81  5071.4 1309.27  5077.6 1308.03    5086 1309.81
  5150.1 1308.99  5249.9 1310.95  5292.4 1313.33    5307 1316.12  5327.8 1317.97
    5357 1322.66  5377.9 1324.48  5407.1 1328.77  5477.9 1332.55    5556 1333.69
#Mann= 3 ,-1 , 0
    3966     .05       0  4975.1     .03       0  5019.8     .05       0
Bank Sta=4975.1,5019.8
XS Rating Curve= 0 ,0
Exp/Cntr=0.3,0.1

Type RM Length L Ch R = 1 ,97000   ,500,500,500
BEGIN DESCRIPTION:
SAN FERNANDO CREEK 194.0
END DESCRIPTION:
XS GIS Cut Line= 3
       2733855.7     10282303.13      2733586.92     10281918.06
      2732755.72     10281353.14
#Sta/Elev= 30
  4530.4 1325.99  4603.3  1321.9  4774.3 1316.75  4817.9 1316.21  4838.8 1318.01
  4859.7 1309.63  4866.9 1302.18  4867.9 1301.68  4911.8 1302.18  4919.1 1304.45
  4946.1 1304.37  4969.4 1306.76  4975.8 1305.45  4981.8 1306.33  4990.6 1303.93
  5003.8 1303.15  5033.6 1303.64    5062 1306.91  5111.5 1306.33  5126.4  1308.2
  5177.3 1309.64  5264.1 1308.31  5291.7 1309.58    5321 1308.69  5371.9  1309.7
  5377.9 1311.66  5392.9  1312.4  5644.4 1320.33  5868.8 1331.38    6005 1333.18
#Mann= 3 ,-1 , 0
  4530.4     .05       0  4866.9     .03       0  4911.8     .05       0
Bank Sta=4866.9,4911.8
XS Rating Curve= 0 ,0
Exp/Cntr=0.3,0.1

Type RM Length L Ch R = 1 ,96500   ,630,630,630
BEGIN DESCRIPTION:
SAN FERNANDO CREEK 193.0
END DESCRIPTION:
XS GIS Cut Line= 3
      2734155.67     10281953.09      2733889.86     10281542.29
      2732782.04     10281228.14
#Sta/Elev= 30
  4510.7 1323.89  4793.3  1314.6  4829.6 1311.55  4850.7 1307.76  4865.8 1304.28
  4871.8 1302.02  4938.4  1304.2  4944.3 1303.35  4974.7  1303.9  4995.8 1302.13
  5012.4    1303  5013.1 1300.94  5014.1 1300.44    5058 1300.94  5066.7 1303.27
  5090.7 1303.62  5108.3 1309.05  5124.6 1312.29  5170.6  1313.7  5326.6  1315.7
  5399.3 1315.54  5562.8 1318.04  5763.1 1319.02  5860.1 1321.08    5919 1323.76
    5928 1325.03  5939.8 1323.28  5950.2 1323.29  6033.4 1326.49  6151.5 1328.64
#Mann= 3 ,-1 , 0
  4510.7     .05       0  5013.1     .03       0    5058     .05       0
Bank Sta=5013.1,5058
XS Rating Curve= 0 ,0
Exp/Cntr=0.3,0.1

Type RM Length L Ch R = 1 ,95870   ,870,870,870
BEGIN DESCRIPTION:
Mapping XS 2463c921
END DESCRIPTION:
XS GIS Cut Line= 4
       2734310.3     10281257.74      2734045.44     10280949.64
      2733499.58     10280841.55      2732598.82      10280803.8
#Sta/Elev= 30
  4475.2 1314.94  4587.7 1314.42  4673.3 1312.46  4751.2 1309.08  4808.2 1308.38
  4829.1 1305.42  4911.8 1305.94  4990.3 1300.45  5064.7 1300.63  5070.3 1299.35
  5071.3 1298.85  5115.2 1299.35  5115.7  1300.2    5144 1301.08  5149.1  1300.4
  5166.7 1303.41  5176.9  1307.4  5187.1 1309.91  5207.5 1311.89    5354 1314.33
  5511.9 1312.72    5662 1314.18  5732.1 1316.12  5812.2 1320.08  6002.5  1330.9
  6052.4 1333.99  6062.4 1335.46  6152.5 1336.34  6242.6 1339.16  6339.5 1340.28
#Mann= 3 ,-1 , 0
  4475.2     .05       0  5070.3     .03       0  5115.2     .05       0
Bank Sta=5070.3,5115.2
XS Rating Curve= 0 ,0
Exp/Cntr=0.3,0.1

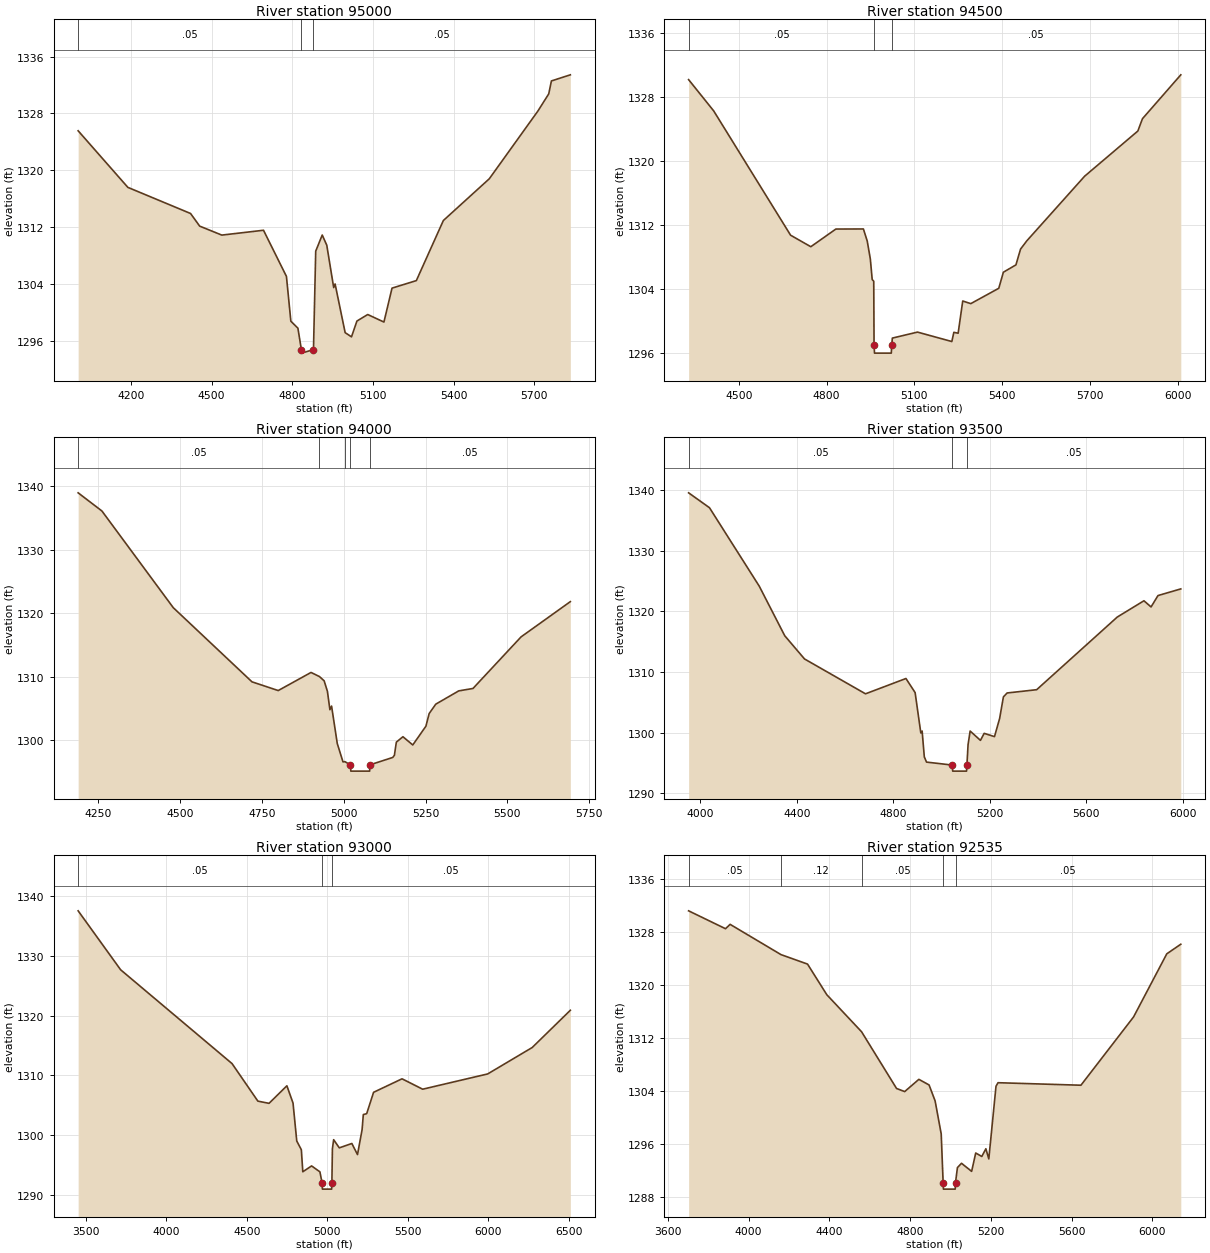
Type RM Length L Ch R = 1 ,95000   ,500,500,500
BEGIN DESCRIPTION:
SAN FERNANDO CREEK 190.0
END DESCRIPTION:
XS GIS Cut Line= 3
      2734855.69     10279853.11      2733885.94     10280078.48
      2733055.68     10280153.11
#Sta/Elev= 30
  4004.4 1325.56  4189.2  1317.6  4422.1 1313.93  4456.1 1312.15  4538.3 1310.89
  4693.3 1311.57  4778.5 1305.08  4794.9 1298.78  4821.1  1297.8    4834 1294.79
    4835 1294.29    4879 1294.79  4887.3 1308.63  4911.5  1310.9  4928.4 1309.47
  4954.1 1303.51  4959.3 1304.02  4996.7 1297.17  5020.3 1296.58  5040.4  1298.8
  5080.6 1299.72  5140.8 1298.66  5170.9 1303.43  5261.3 1304.49  5361.7 1312.94
  5532.4 1318.81  5713.1 1328.34  5753.3 1330.75  5763.3 1332.57  5833.6 1333.43
#Mann= 3 ,-1 , 0
  4004.4     .05       0    4834     .03       0    4879     .05       0
Bank Sta=4834,4879
XS Rating Curve= 0 ,0
Exp/Cntr=0.3,0.1

Type RM Length L Ch R = 1 ,94500   ,500,500,500
BEGIN DESCRIPTION:
SAN FERNANDO CREEK 189.0
END DESCRIPTION:
XS GIS Cut Line= 3
      2734605.71      10279353.1      2733978.83     10279593.51
      2733105.67     10280103.12
#Sta/Elev= 30
  4328.6 1330.21  4414.3  1326.3  4677.2 1310.75  4746.3 1309.31    4832 1311.52
  4926.1 1311.53  4939.1 1310.03  4949.8 1307.77  4956.1 1305.21  4961.4 1304.99
  4962.5    1297    4964    1296  5021.4    1296  5022.9    1297    5025 1297.88
    5111 1298.63  5228.4 1297.45  5235.2  1298.6  5249.9 1298.49  5265.6 1302.52
  5293.1 1302.19  5388.8 1304.11  5404.5 1306.12  5447.5 1307.04  5463.2 1309.01
  5484.7 1310.05  5682.3 1318.13  5864.2 1323.78  5879.9 1325.32    6011 1330.81
#Mann= 3 ,-1 , 0
  4328.6     .05       0  4962.5     .03       0  5022.9     .05       0
Bank Sta=4962.5,5022.9
XS Rating Curve= 0 ,0
Exp/Cntr=0.3,0.1

Type RM Length L Ch R = 1 ,94000   ,500,500,500
BEGIN DESCRIPTION:
SAN FERNANDO CREEK 188.0
END DESCRIPTION:
XS GIS Cut Line= 3
      2734755.65     10279153.11      2733945.71     10279095.27
      2733255.73     10279153.11
#Sta/Elev= 30
    4188    1339  4260.7 1336.13  4478.7 1320.87  4719.3 1309.16  4799.5 1307.78
  4899.8 1310.64  4925.6 1309.99  4939.9 1309.32  4949.9 1307.66  4957.5 1304.76
  4962.6 1305.33    4980 1299.42  4997.5 1296.52  5003.4 1296.55    5020 1296.06
  5021.5 1295.06  5078.9 1295.06  5080.4 1296.06  5149.6 1297.22  5154.6 1297.56
  5160.6 1299.64  5180.7 1300.49  5210.8 1299.19  5250.9 1302.15  5260.9 1304.15
    5281 1305.63  5351.3 1307.73  5394.8 1308.11  5541.9 1316.26  5692.4 1321.82
#Mann= 5 ,-1 , 0
    4188     .05       0  4925.6     .12       0  5003.4     .05       0
    5020     .07       0  5080.4     .05       0
Bank Sta=5020,5080.4
XS Rating Curve= 0 ,0
Exp/Cntr=0.3,0.1

Type RM Length L Ch R = 1 ,93500   ,500,500,500
BEGIN DESCRIPTION:
SAN FERNANDO CREEK 187.0
END DESCRIPTION:
XS GIS Cut Line= 3
      2734845.28     10279014.78      2733880.22     10278605.42
      2733030.01      10279117.1
#Sta/Elev= 30
  3951.7  1339.6  4038.2 1337.14  4244.6 1324.18  4350.3 1315.99  4432.2 1312.16
  4685.1  1306.4  4852.8 1308.93  4890.8  1306.6  4914.4 1299.94  4919.9 1300.25
  4928.9 1295.98  4938.1 1295.12  5045.1 1294.63  5046.6 1293.63    5104 1293.63
  5105.5 1294.63  5110.3    1298  5118.9 1300.25  5161.6 1298.71  5177.1 1299.87
  5219.9 1299.33  5241.2 1302.33  5256.8 1305.89  5272.3 1306.54  5394.7 1307.08
  5728.9 1319.08  5839.5 1321.77    5869 1320.75  5897.7 1322.63  5992.3 1323.73
#Mann= 3 ,-1 , 0
  3951.7     .05       0  5045.1     .03       0  5105.5     .05       0
Bank Sta=5045.1,5105.5
XS Rating Curve= 0 ,0
Exp/Cntr=0.3,0.1

Type RM Length L Ch R = 1 ,93000   ,465,465,465
BEGIN DESCRIPTION:
SAN FERNANDO CREEK 186.0
END DESCRIPTION:
XS GIS Cut Line= 3
      2735185.86      10278771.6      2733777.01     10278129.66
      2732630.08     10279111.52
#Sta/Elev= 30
  3451.8 1337.56  3715.7 1327.68    4408 1311.95  4568.5 1305.66  4637.7 1305.29
  4748.7 1308.23  4786.9 1305.33    4810 1298.98  4838.5 1297.51  4847.6 1293.82
  4902.2  1294.8  4953.8 1293.81  4967.8 1291.91  4969.3 1290.91  5026.7 1290.91
  5028.2 1291.91  5031.5 1297.65  5039.2  1299.2  5074.3 1297.83  5152.3 1298.56
  5187.4  1296.7  5215.9 1300.87  5223.6 1303.41  5244.5 1303.56  5287.3 1307.14
    5464  1309.4  5592.4 1307.66  5996.4 1310.22    6273 1314.65  6509.8 1320.89
#Mann= 3 ,-1 , 0
  3451.8     .05       0  4967.8     .03       0  5028.2     .05       0
Bank Sta=4967.8,5028.2
XS Rating Curve= 0 ,0
Exp/Cntr=0.3,0.1

Type RM Length L Ch R = 1 ,92535   ,1432,1432,1432
BEGIN DESCRIPTION:
Mapping XS 015ecae6
END DESCRIPTION:
XS GIS Cut Line= 3
      2735150.11     10277806.61      2733559.82     10277646.89
      2733198.69     10276889.91
#Sta/Elev= 30
  3703.4 1331.25  3886.1 1328.55  3908.9 1329.21  4160.9 1324.64  4292.3 1323.21
  4387.6 1318.59  4559.8    1313    4733 1304.44  4773.2 1303.97  4843.5 1305.82
    4894 1304.97  4923.9 1302.57  4954.1 1297.58  4963.6 1290.25  4965.1 1289.25
  5023.4 1289.25  5024.9 1290.25  5034.5  1292.5  5054.6 1293.15  5104.8 1291.93
  5124.9  1294.7  5155.1 1294.18  5175.2 1295.34  5189.8 1293.81  5225.4 1304.78
  5235.5 1305.31  5645.9 1304.93  5906.6 1315.24    6071 1324.76  6140.4 1326.21
#Mann= 5 ,-1 , 0
  3703.4     .05       0  4160.9     .12       0  4559.8     .05       0
  4963.6     .03       0  5024.9     .05       0
Bank Sta=4963.6,5024.9
XS Rating Curve= 0 ,0
Exp/Cntr=0.3,0.1

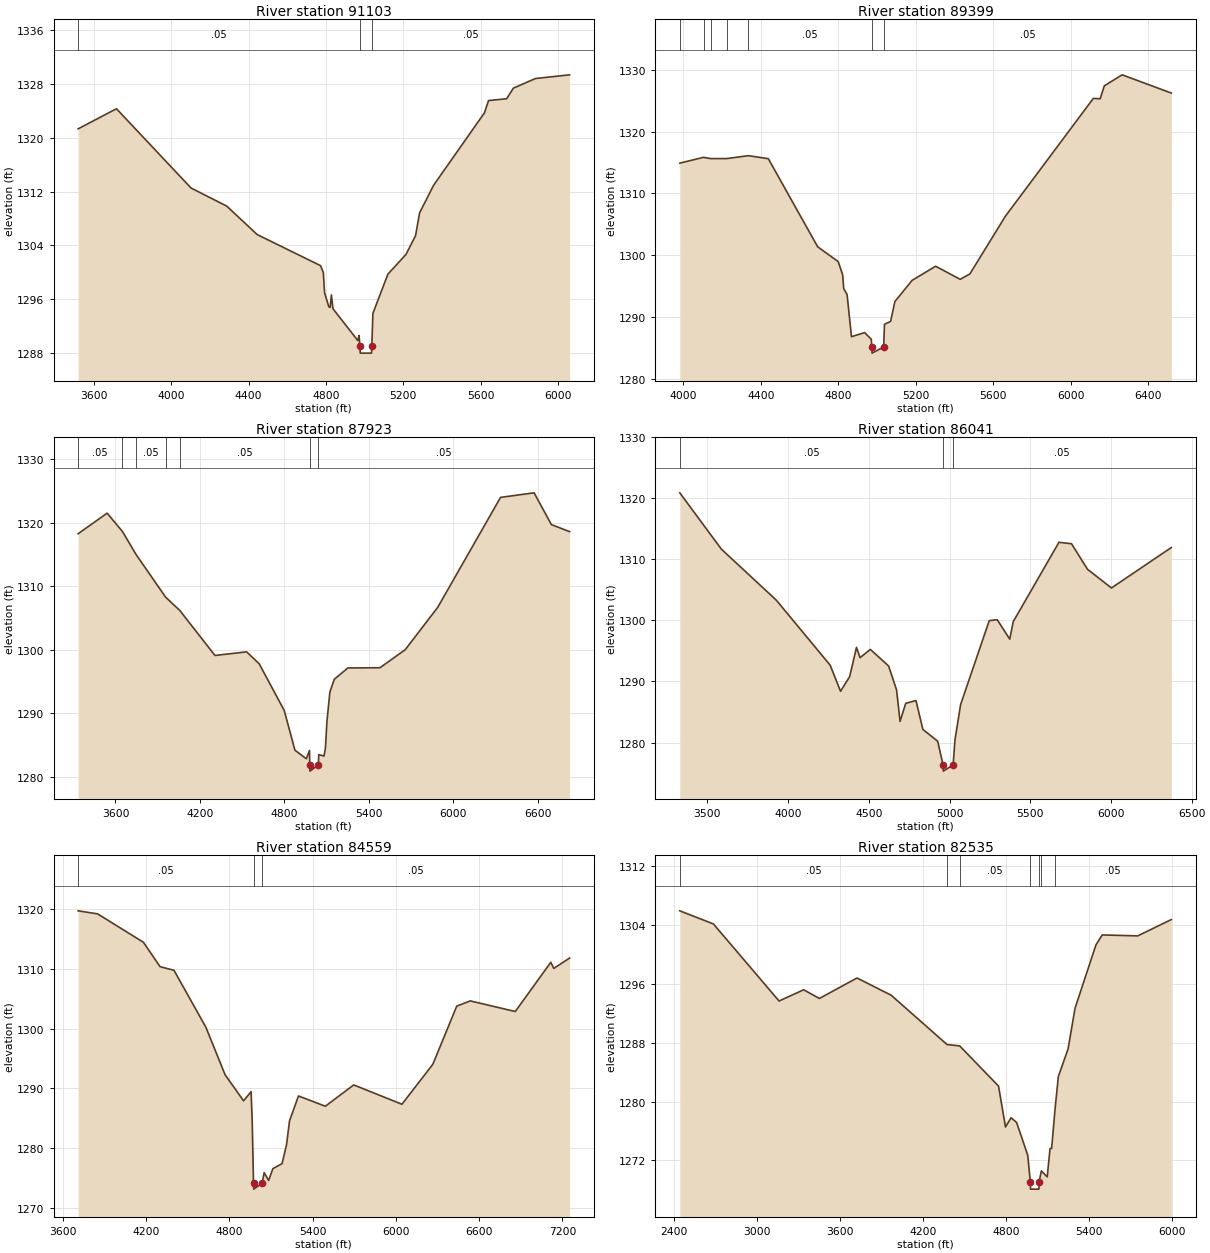
Type RM Length L Ch R = 1 ,91103   ,1704,1704,1704
BEGIN DESCRIPTION:
Mapping XS 8cee7a88
END DESCRIPTION:
XS GIS Cut Line= 2
      2735450.65     10277756.94      2733891.47     10275749.91
#Sta/Elev= 30
  3518.9 1321.32  3717.2 1324.31  4102.8 1312.53  4287.4 1309.84  4444.9 1305.61
  4772.5 1300.99    4787 1299.96  4793.3 1296.97  4815.4 1294.87  4822.3 1294.78
  4828.6 1296.64  4836.8 1294.59  4965.3 1289.86  4971.6 1290.62  4976.2 1288.99
  4977.7 1287.99  5036.1 1287.99  5037.6 1288.99  5043.3  1293.9  5120.9 1299.73
  5214.2 1302.65  5263.9 1305.45  5284.7 1308.83  5357.2 1312.94  5620.5 1323.72
  5641.3 1325.53  5734.6 1325.79  5769.8 1327.37  5883.9  1328.8  6060.4 1329.35
#Mann= 3 ,-1 , 0
  3518.9     .05       0  4976.2     .05       0  5037.6     .05       0
Bank Sta=4976.2,5037.6
XS Rating Curve= 0 ,0
Exp/Cntr=0.3,0.1

Type RM Length L Ch R = 1 ,89399   ,1476,1476,1476
BEGIN DESCRIPTION:
Mapping XS fae36512
END DESCRIPTION:
XS GIS Cut Line= 3
       2736661.5     10277325.65      2736047.79      10276031.9
       2735301.4     10275219.16
#Sta/Elev= 30
  3982.4 1314.88  4104.7 1315.82  4141.1 1315.62  4225.2 1315.62  4336.2 1316.09
    4439  1315.6  4693.6 1301.35  4799.8 1298.94  4822.6 1296.79  4828.1 1294.57
  4845.3 1293.62    4868  1286.8  4936.2 1287.46  4970.3 1286.38  4972.7 1285.14
  4974.2 1284.14  5034.2 1285.14  5038.2  1288.8  5069.9 1289.28    5092 1292.49
  5180.6 1295.91  5302.3  1298.2  5428.9 1296.08  5478.9 1296.96  5662.6 1306.32
  6115.8 1325.36    6151  1325.3  6172.5  1327.4  6264.4 1329.17  6517.8 1326.22
#Mann= 7 ,-1 , 0
  3982.4     .05       0  4104.7     .12       0  4141.1     .05       0
  4225.2     .12       0  4336.2     .05       0  4972.7     .03       0
  5034.2     .05       0
Bank Sta=4972.7,5034.2
XS Rating Curve= 0 ,0
Exp/Cntr=0.3,0.1

Type RM Length L Ch R = 1 ,87923   ,1882,1882,1882
BEGIN DESCRIPTION:
Mapping XS 64b4ca8c
END DESCRIPTION:
XS GIS Cut Line= 3
      2738734.92     10275849.45      2736628.34     10275202.54
      2735369.21     10274937.47
#Sta/Elev= 30
  3334.7  1318.3  3540.8 1321.55  3649.8 1318.65  3745.9 1315.05  3955.7 1308.33
  4057.6  1306.2  4306.8 1299.13  4531.6  1299.7  4620.6 1297.82  4798.4 1290.47
  4874.5 1284.21  4955.3 1282.86  4977.9 1284.16  4979.9 1281.91  4981.4 1280.91
  5041.5 1281.91  5043.4 1283.51  5081.3 1283.29  5091.3 1284.58  5101.8 1288.75
  5122.7 1293.36  5154.1 1295.38  5250.2 1297.16  5478.4  1297.2  5657.8 1300.04
  5888.5 1306.71  6334.8 1324.03  6573.2 1324.75  6695.9 1319.74  6825.1 1318.64
#Mann= 7 ,-1 , 0
  3334.7     .05       0  3649.8     .12       0  3745.9     .05       0
  3955.7     .12       0  4057.6     .05       0  4979.9     .03       0
  5041.5     .05       0
Bank Sta=4979.9,5041.5
XS Rating Curve= 0 ,0
Exp/Cntr=0.3,0.1

Type RM Length L Ch R = 1 ,86041   ,1482,1482,1482
BEGIN DESCRIPTION:
Mapping XS 9ef9a3b1
END DESCRIPTION:
XS GIS Cut Line= 3
      2739166.16     10275235.72       2738336.8     10274257.08
      2737159.13     10272946.72
#Sta/Elev= 30
  3329.2 1320.89  3586.7 1311.67  3927.2 1303.31  4261.2 1292.65  4324.9 1288.39
  4381.3 1290.79  4423.8 1295.59  4445.8  1293.9  4509.5 1295.25  4622.6 1292.54
  4671.9 1288.62  4693.6 1283.47  4728.7 1286.42  4792.3 1286.88  4834.9 1282.16
  4926.8 1280.21  4960.1 1276.32  4961.6 1275.32  5022.2 1276.32  5033.7 1280.41
  5068.8 1286.22    5246 1299.95  5295.3 1300.12  5373.1 1296.93  5394.8  1299.8
    5678 1312.79  5755.8 1312.55  5854.4 1308.38  6003.2 1305.31  6373.8 1311.93
#Mann= 3 ,-1 , 0
  3329.2     .05       0  4960.1     .03       0  5022.2     .05       0
Bank Sta=4960.1,5022.2
XS Rating Curve= 0 ,0
Exp/Cntr=0.3,0.1

Type RM Length L Ch R = 1 ,84559   ,2024,2024,2024
BEGIN DESCRIPTION:
Mapping XS 0b890918
END DESCRIPTION:
XS GIS Cut Line= 3
      2739580.83     10275003.51      2739597.42     10273941.93
      2738685.48      10271637.2
#Sta/Elev= 30
  3711.4 1319.74  3851.8 1319.23  4181.9 1314.47  4301.9 1310.38  4401.9 1309.78
  4631.9 1300.23    4770 1292.28  4903.2 1287.91  4957.3 1289.44  4965.4 1284.54
  4974.9 1274.11  4976.4 1273.11    5037 1274.11  5051.5 1275.87  5083.7 1274.56
  5114.1 1276.54  5180.5 1277.38  5212.8 1280.57  5234.3 1284.55  5298.8 1288.72
  5492.4    1287  5696.7 1290.57    6044 1287.33  6266.7 1294.03  6438.8 1303.77
  6535.9 1304.65  6860.3 1302.87  7116.3 1311.12  7137.8 1310.09  7251.7 1311.83
#Mann= 3 ,-1 , 0
  3711.4     .05       0  4974.9     .05       0    5037     .05       0
Bank Sta=4974.9,5037
XS Rating Curve= 0 ,0
Exp/Cntr=0.3,0.1

Type RM Length L Ch R = 1 ,82535   ,1695,1695,1695
BEGIN DESCRIPTION:
Mapping XS 7ddb4490
END DESCRIPTION:
XS GIS Cut Line= 3
      2740032.59     10274712.82      2740847.85     10272974.62
      2741024.75     10271351.73
#Sta/Elev= 30
  2440.1 1305.94  2682.8 1304.16  3157.7 1293.67  3335.2  1295.2  3449.3 1294.02
    3721  1296.8  3967.9 1294.46  4371.4 1287.75  4463.3 1287.56  4743.8  1282.1
  4794.1 1276.53  4834.3 1277.79  4874.5 1277.15    4955 1272.69  4973.7 1269.08
  4975.2 1268.08  5035.5 1268.08    5037 1269.08  5053.4 1270.56  5095.8 1269.75
    5116  1273.6  5127.7 1273.61  5151.7 1278.84  5176.3  1283.4  5246.7 1287.17
    5297  1292.7  5447.9  1301.3  5493.4 1302.66  5749.7 1302.53  5992.5 1304.75
#Mann= 7 ,-1 , 0
  2440.1     .05       0  4371.4     .12       0  4463.3     .05       0
  4973.7     .03       0    5037     .05       0  5053.4     .12       0
  5151.7     .05       0
Bank Sta=4973.7,5037
XS Rating Curve= 0 ,0
Exp/Cntr=0.3,0.1