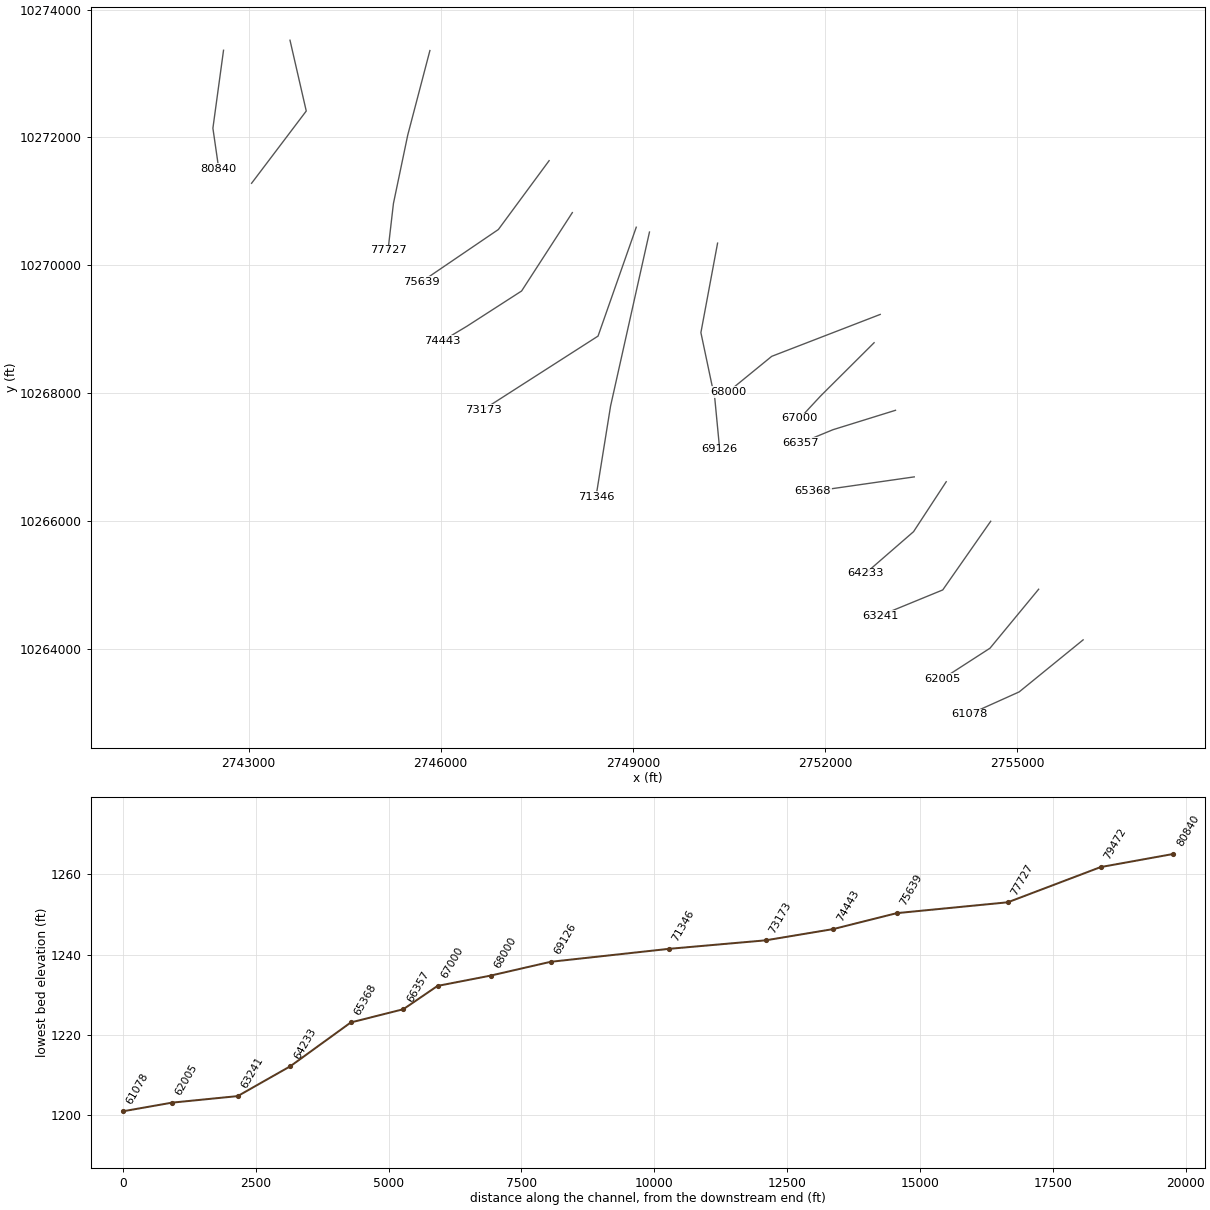
HEC-RAS study SAN FERNANDO CREEK.prj: SAN FERNANDO CREEK Base Level Engineering

--- SAN FERNANDO CREEK.g01 (geometry) --- (continued)

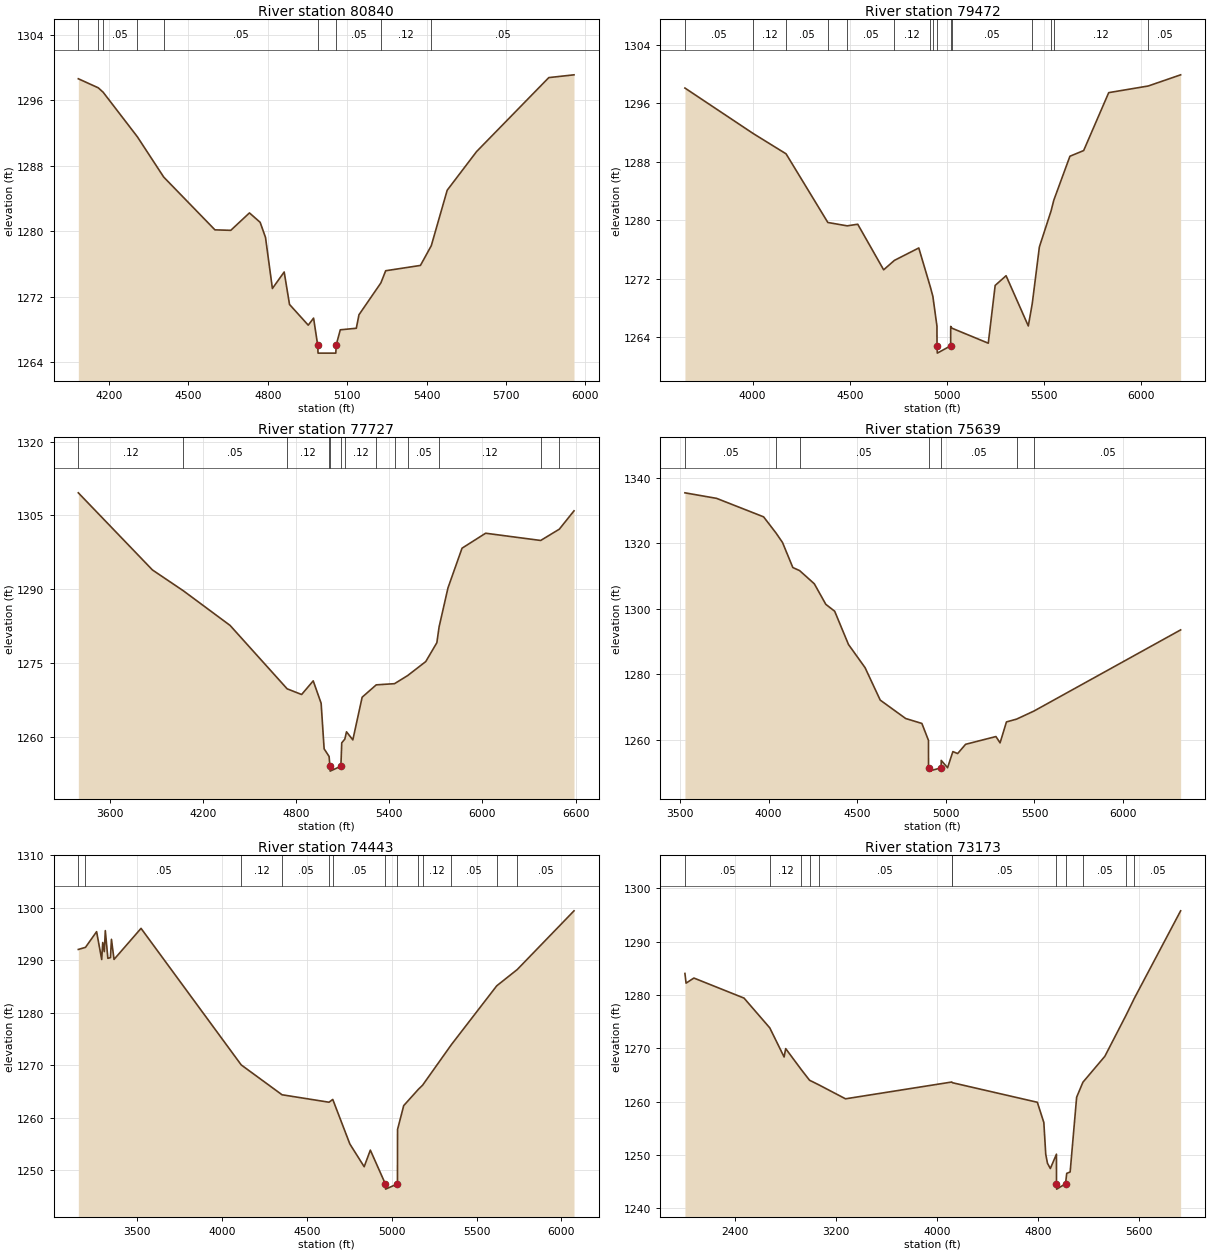
Type RM Length L Ch R = 1 ,80840   ,1368,1368,1368
BEGIN DESCRIPTION:
Mapping XS 5d6c70a6
END DESCRIPTION:
XS GIS Cut Line= 3
      2742609.73     10273363.84      2742443.69     10272144.32
      2742535.31     10271508.76
#Sta/Elev= 30
  4084.4 1298.62  4159.9 1297.51  4178.3 1296.97  4307.4 1291.53  4407.1  1286.6
  4600.6 1280.15  4660.4 1280.09    4731 1282.22  4771.4 1281.07  4791.6 1279.23
  4817.7 1272.98  4862.2    1275  4882.4 1271.03  4953.1  1268.5  4973.3 1269.36
  4988.7 1266.08  4990.2 1265.08  5057.3 1265.08  5058.8 1266.08  5074.2 1267.93
  5134.7 1268.12  5144.8 1269.77  5227.5 1273.66  5245.7 1275.15    5377  1275.8
    5418 1278.21  5478.1 1284.99  5589.2 1289.72    5862 1298.76  5957.3  1299.1
#Mann= 9 ,-1 , 0
  4084.4     .05       0  4159.9     .12       0  4178.3     .05       0
  4307.4     .12       0  4407.1     .05       0  4988.7     .05       0
  5058.8     .05       0  5227.5     .12       0    5418     .05       0
Bank Sta=4988.7,5058.8
XS Rating Curve= 0 ,0
Exp/Cntr=0.3,0.1

Type RM Length L Ch R = 1 ,79472   ,1745,1745,1745
BEGIN DESCRIPTION:
Mapping XS ec26f1a7
END DESCRIPTION:
XS GIS Cut Line= 3
       2743647.5     10273520.66       2743901.3     10272413.15
      2743047.55      10271282.5
#Sta/Elev= 30
  3651.1 1298.11  4002.7 1291.88    4172  1289.1  4387.1  1279.7  4486.9 1279.24
  4541.1 1279.46  4674.5 1273.22  4729.9 1274.51  4855.5 1276.21  4914.6 1270.91
    4928 1269.59  4949.1  1265.5  4949.4 1262.81  4950.9 1261.81  5019.6 1262.81
  5019.9 1265.47  5026.7 1265.22  5213.4 1263.17  5248.9 1271.08  5305.1 1272.41
  5419.6 1265.53  5439.9 1268.59  5476.6 1276.35  5536.7 1281.27    5551 1282.76
  5633.9 1288.77  5704.7 1289.55  5833.7 1297.48  6037.3 1298.39  6204.1 1299.92
#Mann= 15 ,-1 , 0
  3651.1     .05       0  4002.7     .12       0    4172     .05       0
  4387.1     .12       0  4486.9     .05       0  4729.9     .12       0
  4914.6     .05       0    4928     .12       0  4949.4     .07       0
  5019.6     .12       0  5026.7     .05       0  5439.9     .12       0
  5536.7     .05       0    5551     .12       0  6037.3     .05       0
Bank Sta=4949.4,5019.6
XS Rating Curve= 0 ,0
Exp/Cntr=0.3,0.1

Type RM Length L Ch R = 1 ,77727   ,2088,2088,2088
BEGIN DESCRIPTION:
Mapping XS e093c063
END DESCRIPTION:
XS GIS Cut Line= 4
      2745831.82     10273359.16      2745485.72     10272036.28
      2745262.67     10270967.18      2745178.15     10270237.28
#Sta/Elev= 30
  3395.8  1309.6  3873.4 1293.93  4072.8 1289.69  4373.7 1282.66  4741.6 1269.77
  4834.8 1268.62  4909.5 1271.39  4960.5 1266.84  4979.8 1257.58  5011.8 1256.03
  5017.1 1254.05  5018.6 1253.05  5087.8 1254.05  5093.3  1258.8  5113.1 1259.55
    5124 1261.04  5164.8  1259.4  5224.8 1268.07  5315.6 1270.58  5433.4 1270.82
  5517.7 1272.46  5634.7 1275.31  5706.3 1279.15  5720.7 1282.36  5777.8 1290.27
  5868.5 1298.35  6020.5 1301.39  6375.4 1299.92  6495.3 1302.21  6590.1 1305.94
#Mann= 13 ,-1 , 0
  3395.8     .12       0  4072.8     .05       0  4741.6     .12       0
  5011.8     .05       0  5017.1     .07       0  5087.8     .05       0
  5113.1     .12       0  5315.6     .05       0  5433.4     .12       0
  5517.7     .05       0  5720.7     .12       0  6375.4     .05       0
  6495.3     .12       0
Bank Sta=5017.1,5087.8
XS Rating Curve= 0 ,0
Exp/Cntr=0.3,0.1

Type RM Length L Ch R = 1 ,75639   ,1196,1196,1196
BEGIN DESCRIPTION:
Mapping XS 9038a767
END DESCRIPTION:
XS GIS Cut Line= 3
      2747693.12     10271636.32      2746900.92     10270559.54
      2745694.55     10269737.37
#Sta/Elev= 30
  3528.1 1335.42  3706.5 1333.73  3971.9 1328.08  4042.2 1323.12  4078.4 1320.26
  4136.9 1312.58    4175 1311.65  4258.1 1307.61  4322.9 1301.34    4373 1299.22
  4450.8 1289.06  4544.3 1281.99  4629.9 1272.06  4773.6 1266.43  4864.9 1264.93
  4902.2 1259.74  4902.4 1251.35  4903.9 1250.35  4973.8 1251.35    4974 1253.63
  5009.9 1251.39  5039.8 1256.32  5066.8 1255.72  5111.6 1258.55  5282.7 1260.92
  5306.1 1258.99    5342 1265.39  5399.4 1266.25  5497.8 1268.73  6324.8 1293.52
#Mann= 7 ,-1 , 0
  3528.1     .05       0  4042.2     .12       0    4175     .05       0
  4902.4     .03       0  4973.8     .05       0  5399.4     .12       0
  5497.8     .05       0
Bank Sta=4902.4,4973.8
XS Rating Curve= 0 ,0
Exp/Cntr=0.3,0.1

Type RM Length L Ch R = 1 ,74443   ,1270,1270,1270
BEGIN DESCRIPTION:
Mapping XS 6a464028
END DESCRIPTION:
XS GIS Cut Line= 4
       2748055.7     10270823.54      2747263.59     10269597.39
      2746406.39     10269044.01      2746028.28     10268817.15
#Sta/Elev= 30
  3153.2 1292.05  3195.4 1292.45  3260.9 1295.44    3291 1290.13    3297 1293.37
  3306.2 1291.64  3312.2 1295.64  3327.3 1290.36  3342.5 1290.49  3348.4 1293.98
  3363.6 1290.15  3522.8 1296.07  4113.1 1270.05  4353.7 1264.36  4630.4 1262.94
  4652.6 1263.47  4753.2 1254.99  4837.7 1250.65    4874 1253.81  4962.4 1247.38
  4963.9 1246.38  5033.8 1247.38  5034.3 1257.74  5070.6 1262.29  5157.6 1265.42
  5181.6 1266.17    5352 1273.93  5618.8 1285.12  5739.6 1288.22  6074.2 1299.41
#Mann= 13 ,-1 , 0
  3153.2     .12       0  3195.4     .05       0  4113.1     .12       0
  4353.7     .05       0  4630.4     .12       0  4652.6     .05       0
  4962.4     .07       0  5033.8     .05       0  5157.6     .05       0
  5181.6     .12       0    5352     .05       0  5618.8     .12       0
  5739.6     .05       0
Bank Sta=4962.4,5033.8
XS Rating Curve= 0 ,0
Exp/Cntr=0.3,0.1

Type RM Length L Ch R = 1 ,73173   ,1827,1827,1827
BEGIN DESCRIPTION:
Mapping XS 8ef4ed64
END DESCRIPTION:
XS GIS Cut Line= 3
      2749053.95     10270595.63      2748457.17      10268892.1
      2746666.82     10267741.94
#Sta/Elev= 30
  2000.3 1284.01  2009.2 1282.19  2071.3 1283.15  2469.2 1279.39  2673.4 1273.81
  2787.1 1268.35  2799.8 1269.92  2923.9 1265.97    2989 1263.99  3060.2 1263.16
  3274.5 1260.51  4117.8 1263.66    4122 1263.53  4796.4 1259.86  4847.9 1256.07
  4863.1 1250.12  4876.8 1248.43  4899.5 1247.44  4948.1 1250.13  4948.3 1244.58
  4949.8 1243.58  5019.8 1244.58  5029.6 1246.53  5056.7  1246.8  5108.2 1260.81
    5158 1263.62  5332.1 1268.48  5499.4 1276.14  5566.8 1279.39  5933.3 1295.75
#Mann= 12 ,-1 , 0
  2000.3     .05       0  2673.4     .12       0  2923.9     .05       0
    2989     .12       0  3060.2     .05       0  4117.8     .12       0
    4122     .05       0  4948.3     .03       0  5019.8     .05       0
    5158     .05       0  5499.4     .12       0  5566.8     .05       0
Bank Sta=4948.3,5019.8
XS Rating Curve= 0 ,0
Exp/Cntr=0.3,0.1

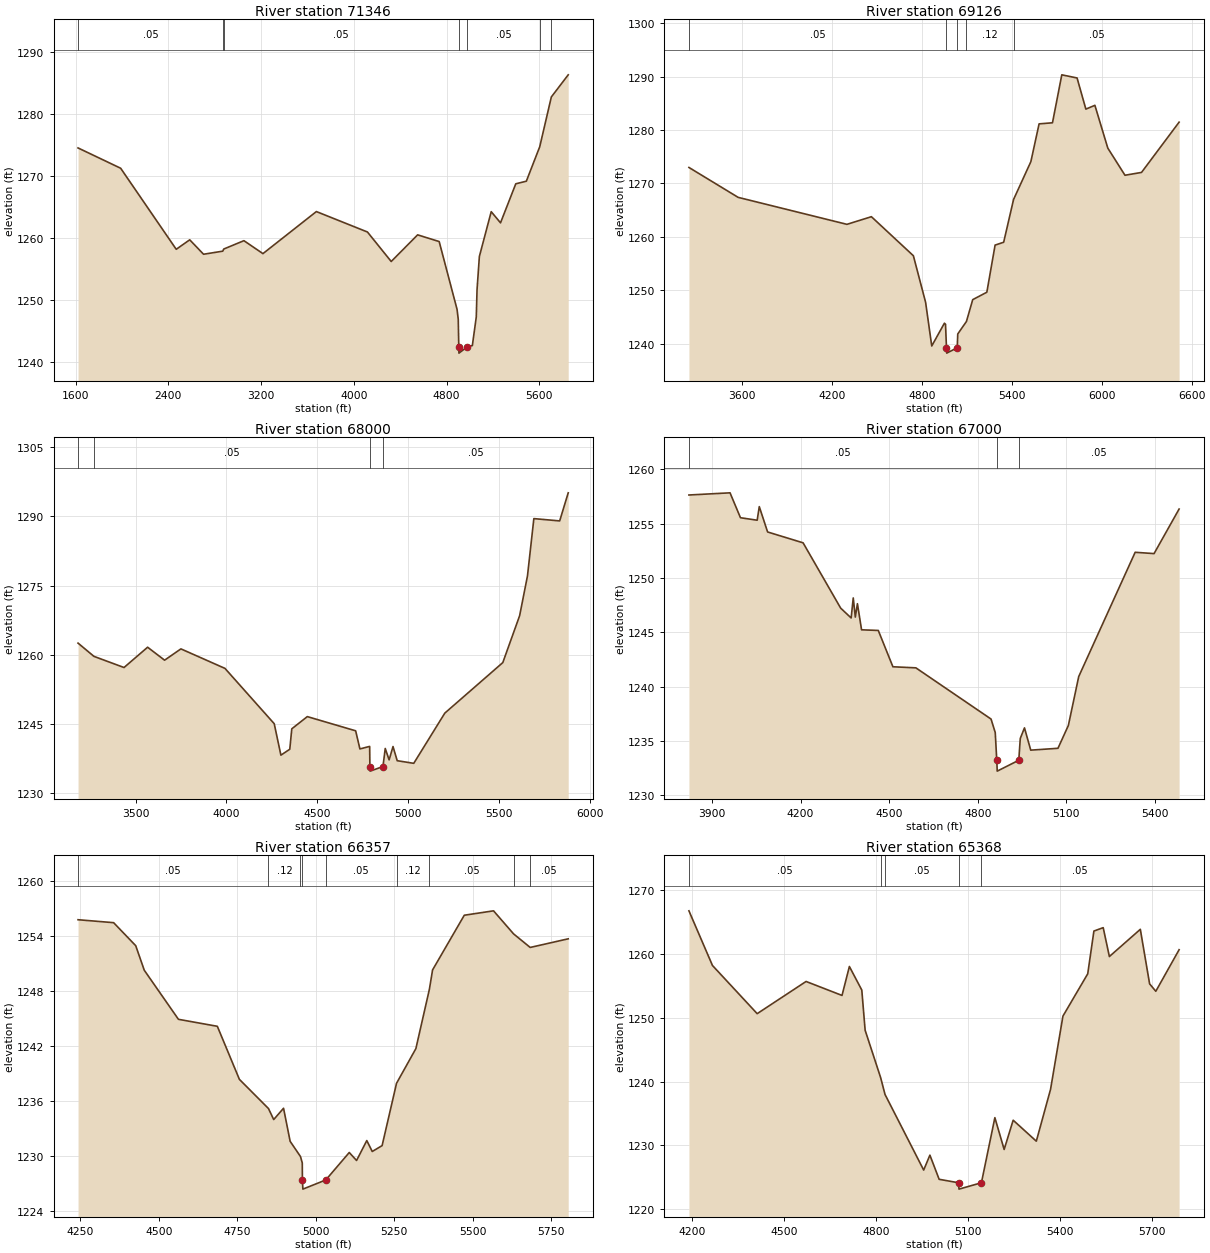
Type RM Length L Ch R = 1 ,71346   ,2220,2220,2220
BEGIN DESCRIPTION:
Mapping XS ffc87140
END DESCRIPTION:
XS GIS Cut Line= 3
      2749260.12     10270519.72      2748652.48     10267796.18
      2748424.88      10266376.4
#Sta/Elev= 30
  1621.2 1274.57  1988.9 1271.29  2468.1 1258.21  2584.5 1259.74  2703.8 1257.41
    2870 1257.91    2878 1258.25  3052.1  1259.6  3216.1 1257.51  3677.1  1264.3
  4117.7    1261  4322.6 1256.24  4550.5 1260.54  4736.4 1259.46  4890.8  1248.5
  4900.9  1246.9  4905.6 1242.45  4907.1 1241.45  4977.2 1242.45  5022.5 1242.67
  5056.4 1247.28    5063 1251.69  5083.2 1257.06  5185.4 1264.28  5265.5 1262.48
  5397.2 1268.78  5488.3  1269.2  5603.8 1274.76    5704  1282.8  5849.6 1286.37
#Mann= 7 ,-1 , 0
  1621.2     .05       0    2870     .12       0    2878     .05       0
  4905.6     .03       0  4977.2     .05       0  5603.8     .12       0
    5704     .05       0
Bank Sta=4905.6,4977.2
XS Rating Curve= 0 ,0
Exp/Cntr=0.3,0.1

Type RM Length L Ch R = 1 ,69126   ,1126,1126,1126
BEGIN DESCRIPTION:
Mapping XS f89bd87b
END DESCRIPTION:
XS GIS Cut Line= 4
       2750323.5     10270346.14      2750063.07     10268946.35
      2750280.09     10267915.54      2750356.04     10267123.39
#Sta/Elev= 30
  3243.4 1272.99    3572 1267.39  4298.4 1262.34  4461.8 1263.77  4742.1 1256.46
  4823.8 1247.73  4864.7 1239.57  4949.2 1243.83  4956.7 1243.64  4963.1 1239.23
  4964.6 1238.23  5034.9 1239.23  5038.4 1241.82  5096.3 1244.15  5138.3 1248.24
  5232.6 1249.63  5287.7 1258.45    5345 1258.99    5411 1266.99  5526.6 1274.08
  5581.5 1281.15  5670.9 1281.35  5733.1 1290.33  5835.1 1289.74  5893.8 1283.91
  5954.1 1284.62  6040.3 1276.61    6155 1271.53  6265.5 1272.06  6516.4 1281.47
#Mann= 5 ,-1 , 0
  3243.4     .05       0  4963.1     .05       0  5034.9     .05       0
  5096.3     .12       0    5411     .05       0
Bank Sta=4963.1,5034.9
XS Rating Curve= 0 ,0
Exp/Cntr=0.3,0.1

Type RM Length L Ch R = 1 ,68000   ,1000,1000,1000
BEGIN DESCRIPTION:
SAN FERNANDO CREEK 136.0
END DESCRIPTION:
XS GIS Cut Line= 3
      2752862.85     10269230.92      2751168.97      10268575.4
      2750485.93     10268016.91
#Sta/Elev= 30
  3183.7 1262.55  3271.1 1259.68  3436.8 1257.26  3566.7 1261.66  3660.2 1258.85
    3750  1261.3  3992.6 1257.07  4263.7 1245.08  4300.5 1238.26  4349.4 1239.55
  4360.4 1243.97  4445.9 1246.62    4712 1243.54  4735.5 1239.61  4789.1 1240.16
  4790.4  1235.8  4791.9  1234.8  4862.4  1235.8  4874.9 1239.71  4896.3 1237.24
  4917.7 1240.13  4940.8 1237.06  5031.9 1236.49  5202.8 1247.37  5522.2 1258.33
  5614.8  1268.5  5657.9 1277.11  5693.1 1289.54  5835.2 1289.04  5882.3 1295.13
#Mann= 4 ,-1 , 0
  3183.7     .12       0  3271.1     .05       0  4790.4     .03       0
  4862.4     .05       0
Bank Sta=4790.4,4862.4
XS Rating Curve= 0 ,0
Exp/Cntr=0.3,0.1

Type RM Length L Ch R = 1 ,67000   ,643,643,643
BEGIN DESCRIPTION:
SAN FERNANDO CREEK 134.0
END DESCRIPTION:
XS GIS Cut Line= 3
      2752767.38     10268788.22      2751933.38     10267956.28
      2751605.67      10267603.1
#Sta/Elev= 30
    3822 1257.63  3961.2 1257.83  3996.5 1255.54  4053.1 1255.31  4060.2 1256.56
  4088.4 1254.23  4208.6 1253.23  4335.9 1247.22  4371.3 1246.32  4378.4 1248.16
  4385.4  1246.4  4392.5 1247.63  4406.6 1245.23  4463.2 1245.17  4512.7 1241.83
  4590.5 1241.73    4845 1237.02  4859.2 1235.78  4864.4 1233.23  4865.9 1232.23
  4938.9 1233.23    4944 1235.24  4958.2 1236.21  4979.4 1234.16  5071.6 1234.33
  5106.8 1236.43  5141.9 1240.93    5333 1252.36    5397 1252.24  5481.8 1256.34
#Mann= 3 ,-1 , 0
    3822     .05       0  4864.4     .05       0  4938.9     .05       0
Bank Sta=4864.4,4938.9
XS Rating Curve= 0 ,0
Exp/Cntr=0.3,0.1

Type RM Length L Ch R = 1 ,66357   ,989,989,989
BEGIN DESCRIPTION:
Mapping XS a79f45c4
END DESCRIPTION:
XS GIS Cut Line= 3
      2753101.31     10267731.09       2752124.7     10267427.25
      2751625.59      10267221.1
#Sta/Elev= 30
  4242.2 1255.78  4355.6 1255.46  4426.1 1252.95  4453.3 1250.28  4562.3 1244.93
  4686.3 1244.17  4756.6 1238.39  4849.3 1235.21    4866 1234.01  4897.4 1235.24
  4918.4 1231.64  4951.4 1229.98  4957.1 1229.28  4957.5 1227.43    4959 1226.43
  5032.1 1227.43  5106.9 1230.42  5130.2 1229.55  5162.8 1231.72  5180.2 1230.53
  5211.6 1231.17  5257.6 1237.96  5319.3 1241.74  5362.3 1248.19  5372.5 1250.31
  5473.6 1256.27  5566.9 1256.75  5630.7 1254.24  5683.8 1252.76    5805  1253.7
#Mann= 9 ,-1 , 0
  4242.2     .05       0  4849.3     .12       0  4951.4     .05       0
  4957.5     .05       0  5032.1     .05       0  5257.6     .12       0
  5362.3     .05       0  5630.7     .12       0  5683.8     .05       0
Bank Sta=4957.5,5032.1
XS Rating Curve= 0 ,0
Exp/Cntr=0.3,0.1

Type RM Length L Ch R = 1 ,65368   ,1135,1135,1135
BEGIN DESCRIPTION:
Mapping XS 5caad5f3
END DESCRIPTION:
XS GIS Cut Line= 2
      2753394.19      10266689.4      2751810.39     10266461.59
#Sta/Elev= 30
  4188.8 1266.78  4265.6 1258.21  4411.6 1250.65  4571.2  1255.7  4688.5 1253.51
  4712.6 1258.05  4753.1 1254.35    4764 1248.05  4814.6 1240.62  4828.9 1237.98
  4955.1 1226.12  4975.4 1228.46  5005.6 1224.67  5068.9 1224.13  5070.4 1223.13
  5143.6 1224.13  5187.5 1234.34  5217.8 1229.35  5247.2 1233.94  5322.8 1230.65
  5369.3 1238.79  5409.7 1250.27  5490.6  1256.9  5510.8 1263.61  5541.1 1264.14
  5561.3 1259.61  5662.3 1263.88  5692.6 1255.33  5712.8 1254.16  5788.9 1260.68
#Mann= 5 ,-1 , 0
  4188.8     .05       0  4814.6     .12       0  4828.9     .05       0
  5068.9     .05       0  5143.6     .05       0
Bank Sta=5068.9,5143.6
XS Rating Curve= 0 ,0
Exp/Cntr=0.3,0.1

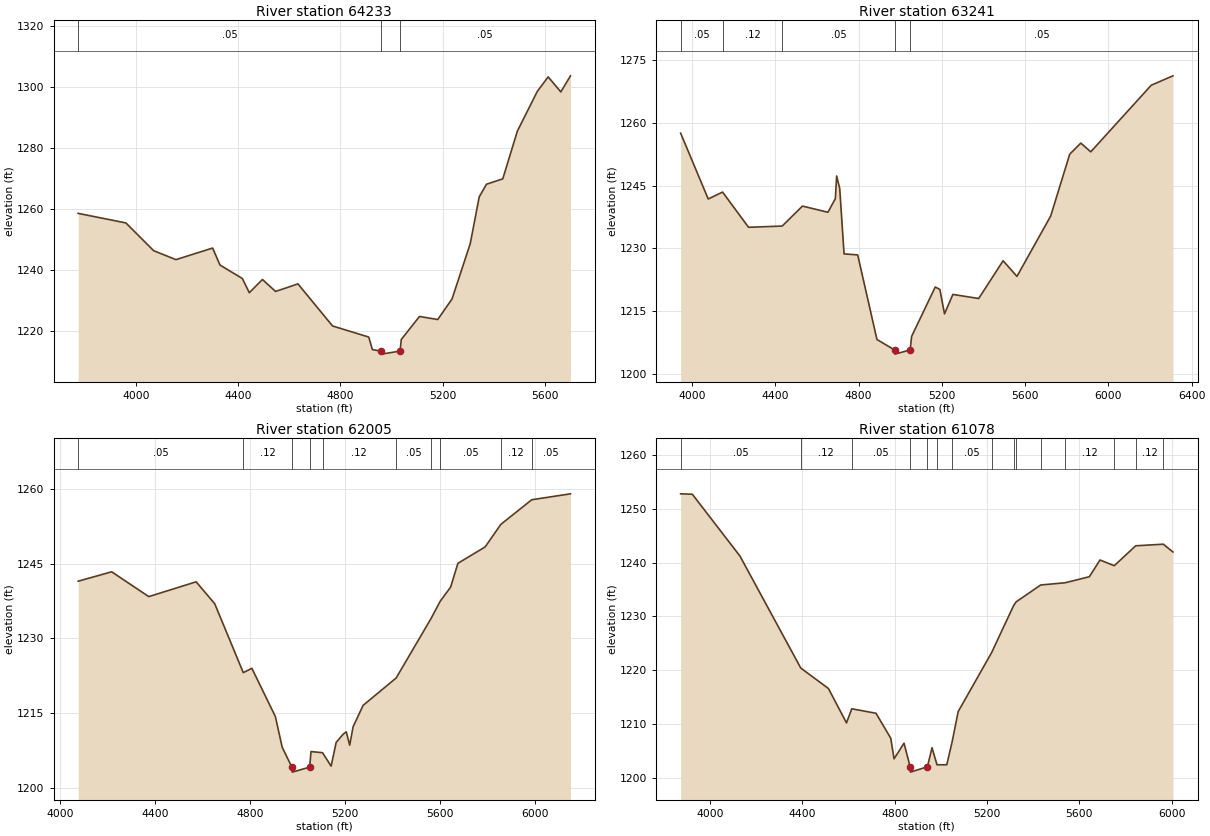
Type RM Length L Ch R = 1 ,64233   ,992,992,992
BEGIN DESCRIPTION:
Mapping XS ff5b154e
END DESCRIPTION:
XS GIS Cut Line= 3
      2753893.36     10266613.44      2753383.38      10265832.2
      2752634.71     10265181.18
#Sta/Elev= 30
    3775 1258.47  3961.7 1255.33  4070.3 1246.21  4157.5 1243.28  4300.8 1247.08
  4329.7  1241.5  4417.2 1237.07  4444.3 1232.42  4495.6 1236.76  4546.9 1232.83
  4634.5 1235.31  4769.8  1221.5  4911.3 1217.85  4925.6 1213.73  4959.1 1213.25
  4960.6 1212.25  5033.8 1213.25  5038.5 1217.06  5109.8 1224.62    5181 1223.61
    5237 1230.36  5308.2 1248.53  5343.3 1263.89  5371.8 1268.04  5435.4  1269.8
  5492.4 1285.46  5570.3  1298.5    5613 1303.29  5662.4 1298.34  5700.1 1303.63
#Mann= 3 ,-1 , 0
    3775     .05       0  4959.1     .03       0  5033.8     .05       0
Bank Sta=4959.1,5033.8
XS Rating Curve= 0 ,0
Exp/Cntr=0.3,0.1

Type RM Length L Ch R = 1 ,63241   ,1236,1236,1236
BEGIN DESCRIPTION:
Mapping XS 607ecd4a
END DESCRIPTION:
XS GIS Cut Line= 3
      2754587.82     10265994.98      2753839.11     10264920.74
      2752862.53     10264519.26
#Sta/Elev= 30
  3944.8 1257.52  4077.4 1241.81  4146.3 1243.46  4271.1 1235.06  4432.7 1235.35
  4530.2 1240.12  4652.4 1238.64  4688.2 1241.89  4694.3 1247.29  4709.1 1244.33
    4730 1228.71  4795.5 1228.47    4888 1208.29  4972.7  1205.8  4974.2  1204.8
  5047.5  1205.8  5054.6 1209.03  5168.1 1220.81  5190.4 1220.22  5212.6 1214.41
  5252.8 1219.04  5376.8 1218.07  5494.1 1227.07  5560.7 1223.35  5722.8 1237.75
  5814.1 1252.49  5867.4 1255.14  5915.3 1253.06  6205.9 1268.95  6310.1 1271.19
#Mann= 5 ,-1 , 0
  3944.8     .05       0  4146.3     .12       0  4432.7     .05       0
  4972.7     .03       0  5047.5     .05       0
Bank Sta=4972.7,5047.5
XS Rating Curve= 0 ,0
Exp/Cntr=0.3,0.1

Type RM Length L Ch R = 1 ,62005   ,927,927,927
BEGIN DESCRIPTION:
Mapping XS 80daf346
END DESCRIPTION:
XS GIS Cut Line= 3
      2755336.53     10264931.62      2754576.96     10264009.29
      2753839.93     10263532.39
#Sta/Elev= 30
  4075.7 1241.49  4216.7 1243.38  4373.1  1238.4  4572.5 1241.37  4650.7 1236.97
  4770.9 1223.14  4807.1 1224.01  4906.1 1214.31  4934.8 1208.15  4975.5 1204.17
    4977 1203.17  5050.4 1204.17    5056  1207.3  5104.7 1207.07  5140.7 1204.37
  5161.9 1209.13  5190.2 1210.72  5204.5 1211.27  5218.9 1208.58  5233.2 1212.27
  5275.4 1216.57  5414.6 1222.07  5561.5 1234.01  5599.5 1237.43    5644 1240.32
  5674.4 1245.08  5789.1 1248.37  5855.3  1252.9  5985.3 1257.84  6148.4 1259.03
#Mann= 10 ,-1 , 0
  4075.7     .05       0  4770.9     .12       0  4975.5     .05       0
  5050.4     .12       0  5104.7     .12       0  5414.6     .05       0
  5561.5     .12       0  5599.5     .05       0  5855.3     .12       0
  5985.3     .05       0
Bank Sta=4975.5,5050.4
XS Rating Curve= 0 ,0
Exp/Cntr=0.3,0.1

Type RM Length L Ch R = 1 ,61078   ,1080,1080,1080
BEGIN DESCRIPTION:
Mapping XS 1775dd23
END DESCRIPTION:
XS GIS Cut Line= 3
      2756030.98     10264139.51      2755032.69     10263325.69
       2754262.3     10262978.47
#Sta/Elev= 30
  3872.3 1252.84  3923.1 1252.76  4129.2 1241.26  4392.7  1220.4  4512.7 1216.58
  4590.9 1210.18  4613.8 1212.81  4718.8 1211.97  4782.7 1207.32    4797 1203.49
  4840.1  1206.4  4866.6 1202.01  4868.1 1201.01  4941.5 1202.01  4961.5 1205.56
    4983 1202.38  5025.4 1202.38  5048.1 1206.56  5074.9 1212.29  5219.7 1223.27
  5314.9 1232.02    5326 1232.72  5432.2 1235.86  5538.5 1236.28  5643.1  1237.4
  5689.4 1240.52    5751 1239.45  5843.8 1243.16  5963.5 1243.46  6005.3 1242.01
#Mann= 15 ,-1 , 0
  3872.3     .05       0  4392.7     .12       0  4613.8     .05       0
  4866.6     .07       0  4941.5     .05       0    4983     .12       0
  5048.1     .05       0  5219.7     .12       0  5314.9     .05       0
    5326     .12       0  5432.2     .05       0  5538.5     .12       0
    5751     .05       0  5843.8     .12       0  5963.5     .05       0
Bank Sta=4866.6,4941.5
XS Rating Curve= 0 ,0
Exp/Cntr=0.3,0.1