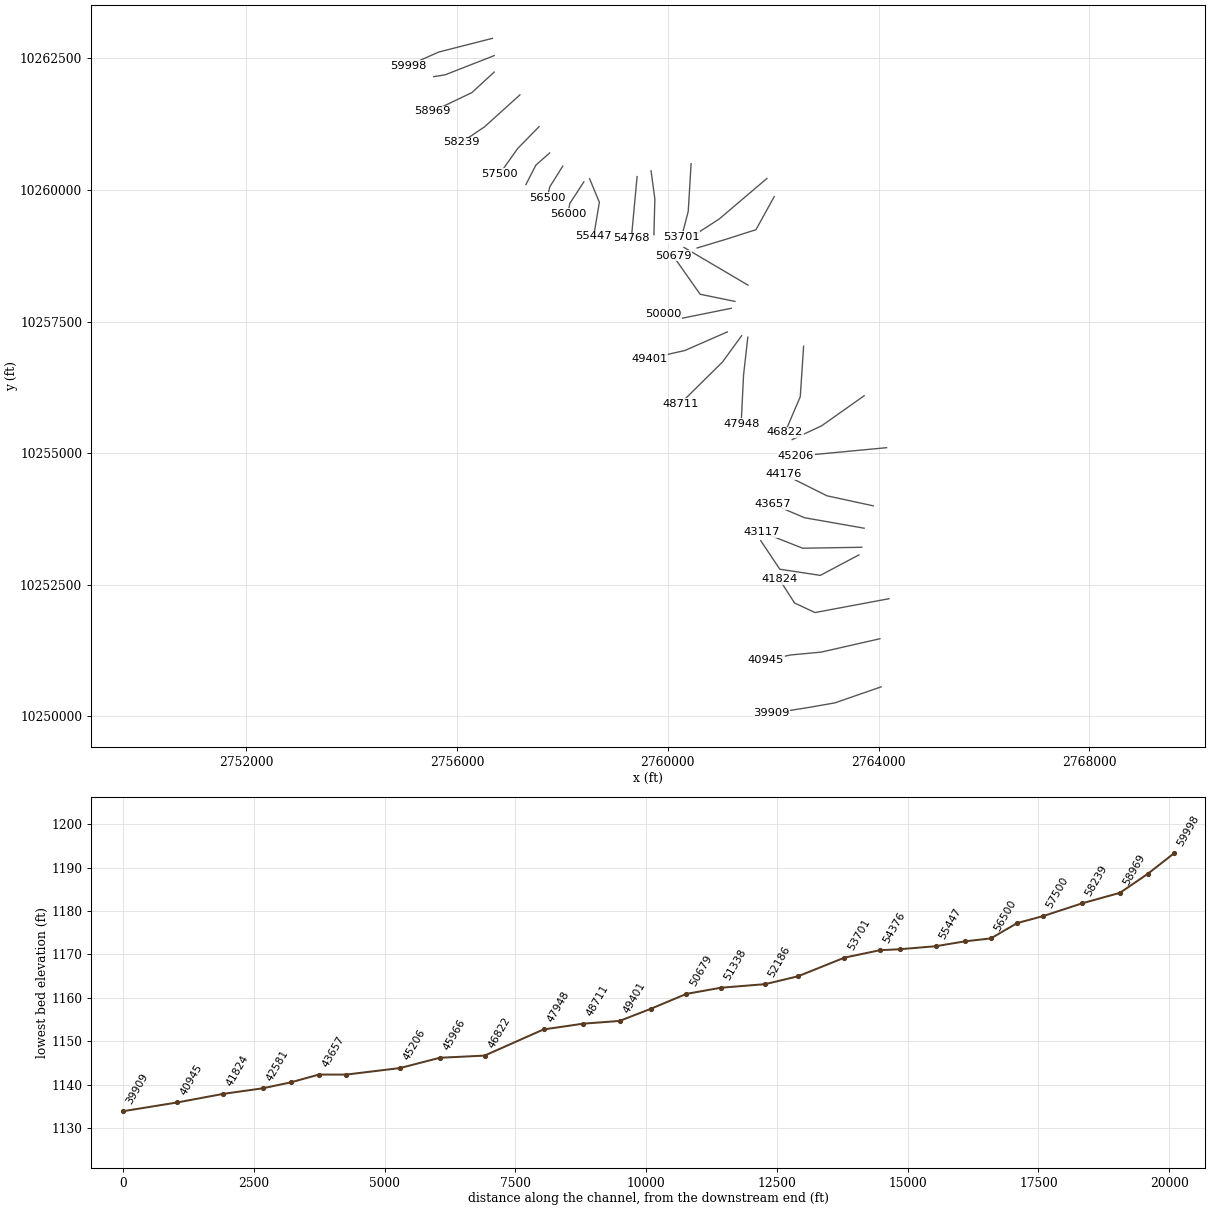
HEC-RAS study SAN FERNANDO CREEK.prj: SAN FERNANDO CREEK Base Level Engineering

--- SAN FERNANDO CREEK.g01 (geometry) --- (continued)

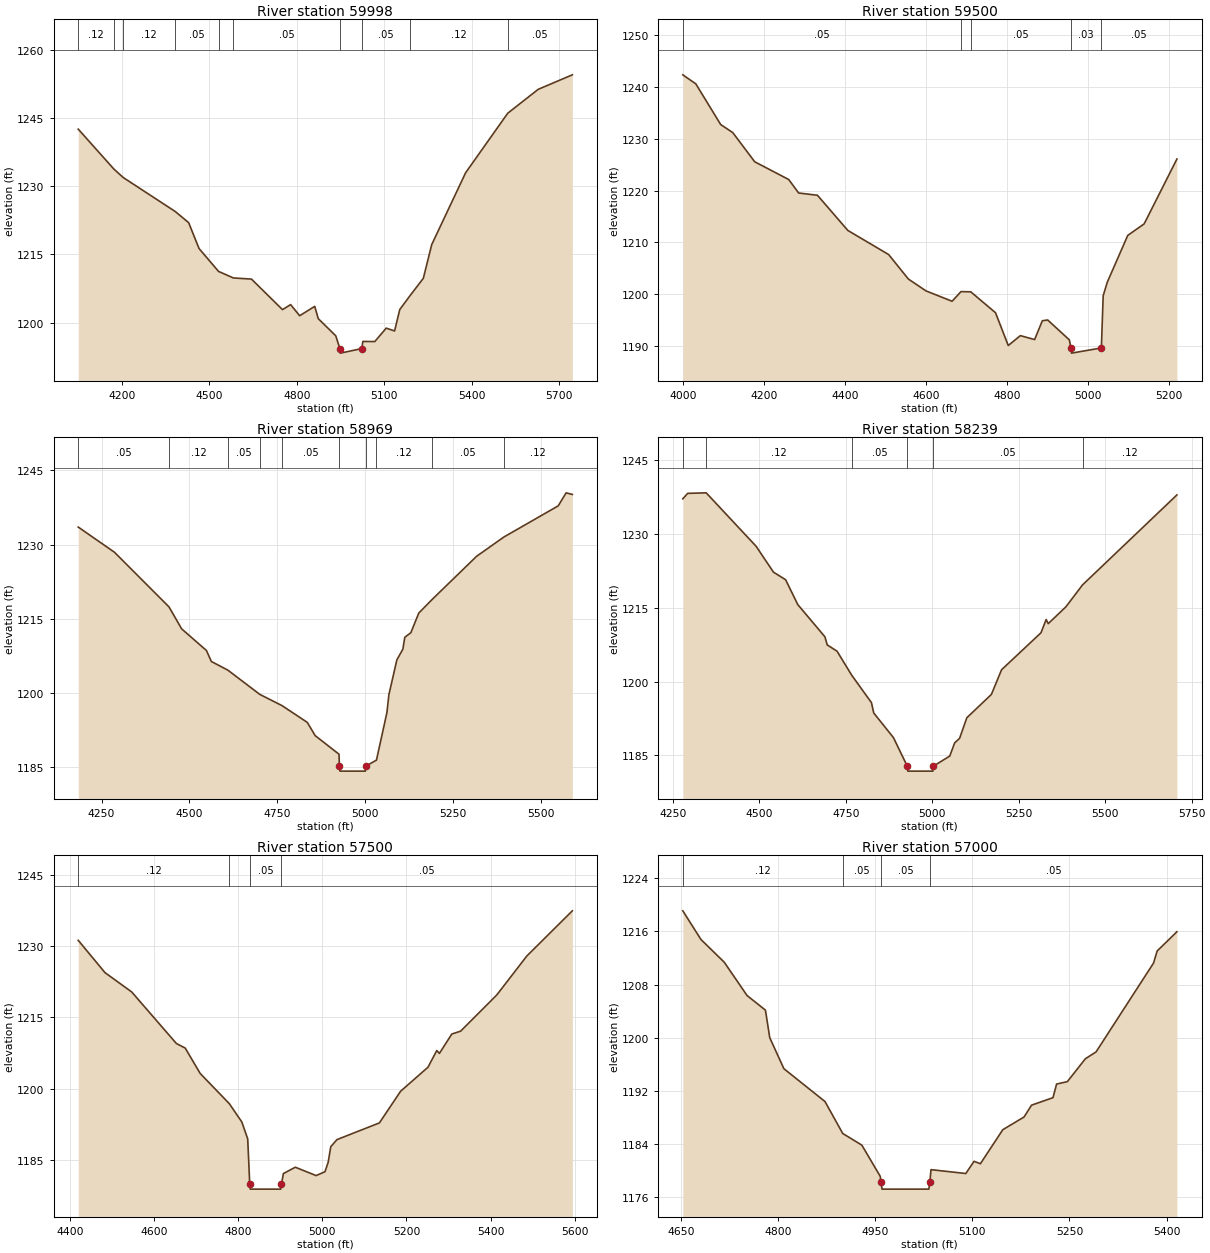
Type RM Length L Ch R = 1 ,59998   ,498,498,498
BEGIN DESCRIPTION:
Mapping XS a6aa63c7
END DESCRIPTION:
XS GIS Cut Line= 3
      2756671.15     10262880.81      2755651.18      10262620.4
      2755065.23     10262359.98
#Sta/Elev= 30
    4051 1242.58    4173 1233.81  4204.9 1231.95  4383.5 1224.46  4429.5 1222.01
  4465.2 1216.31    4532 1211.28  4582.8 1209.84  4644.9 1209.59  4751.2 1202.87
  4779.1 1203.97  4810.1 1201.53  4861.7 1203.59  4873.8 1200.89  4933.9 1197.11
  4947.9  1194.3  4949.4  1193.3  5023.1  1194.3  5026.8 1195.87  5067.7 1195.85
  5106.8  1198.8  5135.5 1198.18  5153.3 1202.89  5188.3 1205.93    5234 1209.76
  5262.9 1217.19    5379 1232.98  5523.4 1246.08  5627.9 1251.34  5744.9 1254.53
#Mann= 10 ,-1 , 0
    4051     .12       0    4173     .05       0  4204.9     .12       0
  4383.5     .05       0    4532     .12       0  4582.8     .05       0
  4947.9     .05       0  5023.1     .05       0  5188.3     .12       0
  5523.4     .05       0
Bank Sta=4947.9,5023.1
XS Rating Curve= 0 ,0
Exp/Cntr=0.3,0.1

Type RM Length L Ch R = 1 ,59500   ,531,531,531
BEGIN DESCRIPTION:
SAN FERNANDO CREEK 119.0
END DESCRIPTION:
XS GIS Cut Line= 3
      2756705.72     10262553.12      2755773.38     10262188.22
      2755555.69     10262153.11
#Sta/Elev= 30
  3998.8 1242.37    4031 1240.62  4092.5 1232.76  4122.3 1231.21  4176.6 1225.57
  4260.7 1222.14  4285.2 1219.54  4331.7  1219.1  4406.9  1212.3  4507.7 1207.65
  4556.6 1202.91  4600.2 1200.62  4664.6 1198.62  4686.7 1200.49  4710.8 1200.44
    4772 1196.41  4803.5 1190.07  4833.4 1191.98  4868.7 1191.22  4887.7 1194.85
  4900.9 1195.01  4954.6 1191.16  4958.5  1189.6    4960  1188.6  5033.7  1189.6
  5038.2 1199.68  5048.3 1202.29    5099 1211.35  5139.5 1213.57  5220.5  1226.1
#Mann= 5 ,-1 , 0
  3998.8     .05       0  4686.7     .12       0  4710.8     .05       0
  4958.5     .03       0  5033.7     .05       0
Bank Sta=4958.5,5033.7
XS Rating Curve= 0 ,0
Exp/Cntr=0.3,0.1

Type RM Length L Ch R = 1 ,58969   ,730,730,730
BEGIN DESCRIPTION:
Mapping XS 5bcac330
END DESCRIPTION:
XS GIS Cut Line= 3
      2756703.66     10262240.59      2756280.52       10261850.
       2755531.8     10261491.91
#Sta/Elev= 30
  4183.7 1233.54  4286.8 1228.45    4442  1217.4  4477.9 1212.97  4548.4  1208.6
  4562.4 1206.38  4609.8 1204.61  4700.4 1199.72  4763.2 1197.47  4835.2 1194.08
  4857.9 1191.39  4925.6 1187.64  4926.8 1185.22  4928.3 1184.22  5000.5 1184.22
    5002 1185.22  5032.2 1186.45    5062 1196.08  5067.5 1199.66  5090.2 1206.69
  5107.3 1208.87  5112.8 1211.27    5130 1212.19  5152.6 1216.16  5189.7 1218.85
  5316.9 1227.62  5394.7 1231.53  5549.2 1237.82  5571.9 1240.46  5589.5 1240.13
#Mann= 10 ,-1 , 0
  4183.7     .05       0    4442     .12       0  4609.8     .05       0
  4700.4     .12       0  4763.2     .05       0  4926.8     .03       0
    5002     .05       0  5032.2     .12       0  5189.7     .05       0
  5394.7     .12       0
Bank Sta=4926.8,5002
XS Rating Curve= 0 ,0
Exp/Cntr=0.3,0.1

Type RM Length L Ch R = 1 ,58239   ,739,739,739
BEGIN DESCRIPTION:
Mapping XS 31f482fe
END DESCRIPTION:
XS GIS Cut Line= 3
        2757192.     10261806.62      2756519.23     10261198.96
       2756086.8     10260907.06
#Sta/Elev= 30
  4279.1 1237.17  4293.1 1238.28  4346.7 1238.39  4491.1 1227.51  4541.2 1222.25
  4576.3 1220.71  4611.4 1215.66  4689.9  1209.1  4696.6 1207.45    4725 1206.17
  4767.4 1201.28  4824.4 1195.71  4831.1 1193.59  4887.9  1188.6    4928 1182.77
  4929.5 1181.77  5001.8 1181.77  5003.3 1182.77  5050.8 1184.84    5065 1187.52
  5079.2 1188.44  5100.1 1192.63  5171.1 1197.37  5200.5 1202.39  5314.5 1209.92
  5329.4 1212.61  5335.5 1211.78  5386.4 1215.19  5434.6 1219.66  5707.4 1237.96
#Mann= 6 ,-1 , 0
  4279.1     .05       0  4346.7     .12       0  4767.4     .05       0
    4928     .03       0  5003.3     .05       0  5434.6     .12       0
Bank Sta=4928,5003.3
XS Rating Curve= 0 ,0
Exp/Cntr=0.3,0.1

Type RM Length L Ch R = 1 ,57500   ,500,500,500
BEGIN DESCRIPTION:
SAN FERNANDO CREEK 115.0
END DESCRIPTION:
XS GIS Cut Line= 3
      2757555.68     10261203.11      2757149.61     10260787.99
      2756805.67     10260303.08
#Sta/Elev= 30
  4419.3 1231.19  4482.9  1224.4  4546.5 1220.33  4652.7 1209.49  4673.8 1208.52
  4709.3 1203.19  4778.6 1196.83  4808.3 1192.99  4822.4 1189.41  4827.2 1179.85
  4828.7 1178.85    4901 1178.85  4902.5 1179.85  4907.3 1182.13  4935.6 1183.46
    4985  1181.7  5006.1 1182.51  5013.8 1184.51  5019.9 1187.77  5034.7 1189.27
  5135.6 1192.78    5186 1199.44  5251.2  1204.5  5272.1 1208.01  5278.3  1207.4
  5307.8 1211.48  5328.7 1212.08  5414.8  1219.7  5486.2 1227.89  5594.5  1237.4
#Mann= 4 ,-1 , 0
  4419.3     .12       0  4778.6     .05       0  4827.2     .05       0
  4902.5     .05       0
Bank Sta=4827.2,4902.5
XS Rating Curve= 0 ,0
Exp/Cntr=0.3,0.1

Type RM Length L Ch R = 1 ,57000   ,500,500,500
BEGIN DESCRIPTION:
SAN FERNANDO CREEK 114.0
END DESCRIPTION:
XS GIS Cut Line= 3
      2757755.72     10260703.14       2757495.7     10260473.06
      2757305.68     10260103.11
#Sta/Elev= 30
  4652.8 1219.09  4680.9 1214.77  4716.8 1211.36    4752 1206.35  4780.4 1204.15
  4787.1    1200  4808.9 1195.34  4872.4  1190.4  4899.8 1185.59  4929.3 1183.84
  4957.7 1179.15    4959 1178.22  4960.5 1177.22  5032.8 1177.22  5034.3 1178.22
  5036.1 1180.15  5089.9 1179.57  5102.6 1181.41  5112.4 1181.04    5147 1186.16
  5179.8 1188.07  5191.4 1189.85  5224.5 1190.98  5230.1 1193.03  5246.7 1193.39
  5274.5 1196.83  5291.1 1197.87  5379.8 1211.23  5385.4 1213.05  5415.9 1215.94
#Mann= 4 ,-1 , 0
  4652.8     .12       0  4899.8     .05       0    4959     .05       0
  5034.3     .05       0
Bank Sta=4959,5034.3
XS Rating Curve= 0 ,0
Exp/Cntr=0.3,0.1

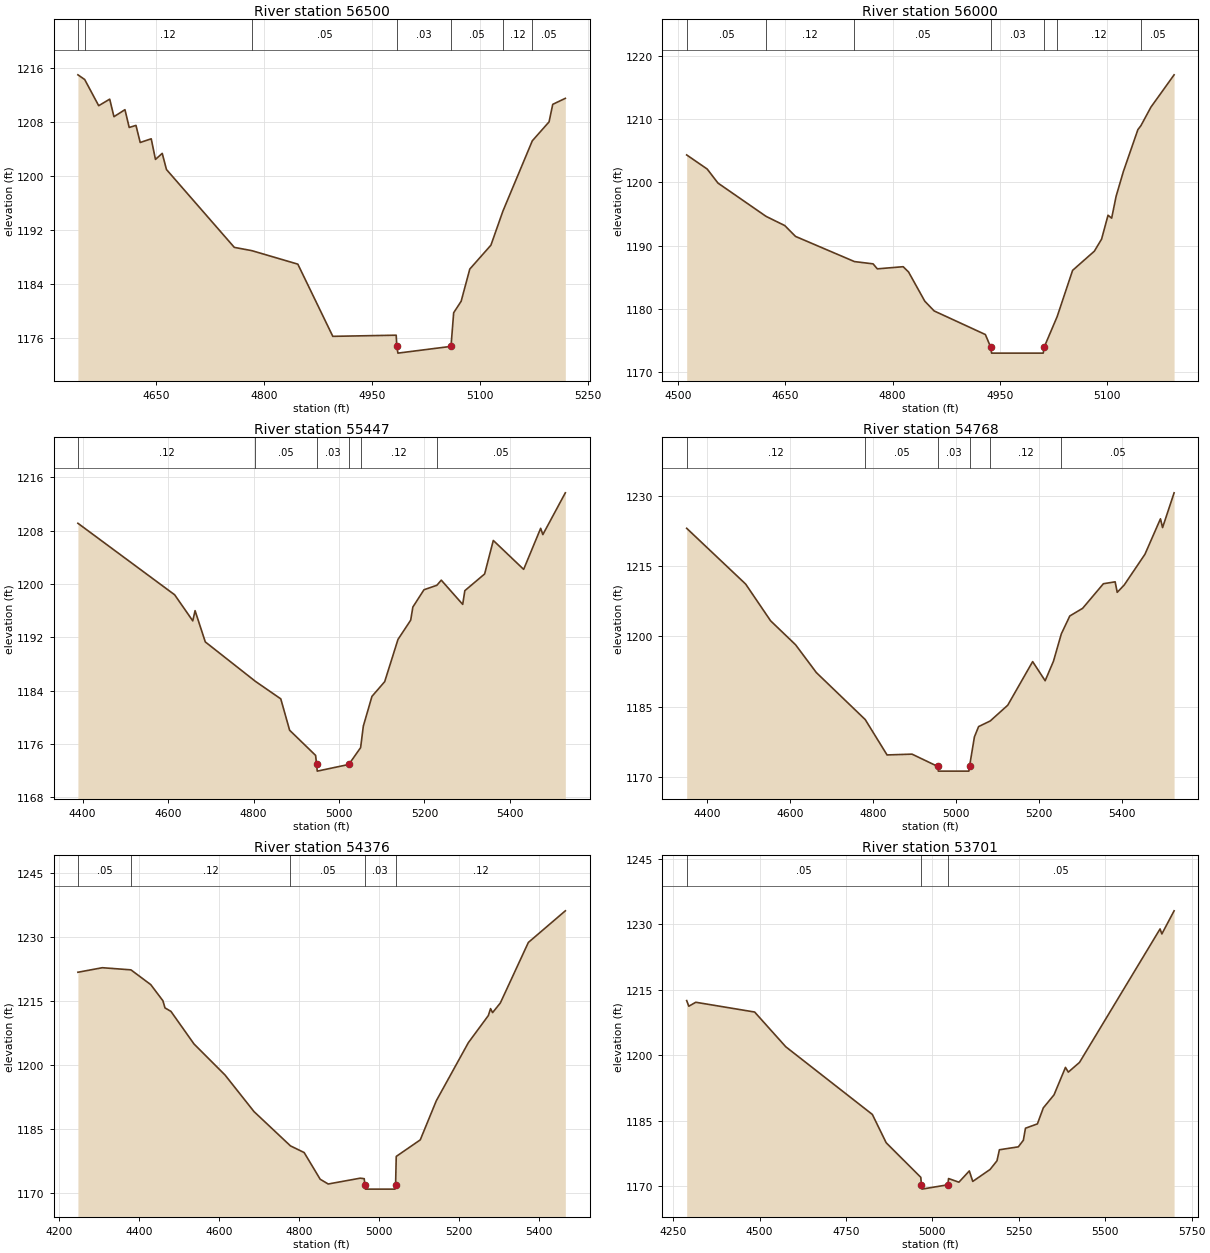
Type RM Length L Ch R = 1 ,56500   ,500,500,500
BEGIN DESCRIPTION:
SAN FERNANDO CREEK 113.0
END DESCRIPTION:
XS GIS Cut Line= 3
       2758005.7     10260453.13      2757761.95     10260064.91
      2757705.69     10259853.15
#Sta/Elev= 30
  4541.6 1214.99    4551  1214.3  4570.5 1210.41  4585.8 1211.38  4591.7 1208.78
    4607 1209.82  4612.9 1207.18  4622.3 1207.49  4628.2 1204.95  4643.5  1205.5
  4649.4 1202.44  4658.8 1203.34  4664.7 1200.94    4759 1189.39  4783.5  1188.9
  4847.3  1186.9  4895.9 1176.19    4984 1176.36  4984.9  1174.7  4986.4  1173.7
  5060.2  1174.7  5063.9 1179.69  5074.3  1181.4  5086.3 1186.17  5115.7 1189.72
  5132.2 1194.73  5173.2  1205.2  5196.5 1208.01  5201.6 1210.61  5219.1  1211.5
#Mann= 7 ,-1 , 0
  4541.6     .05       0    4551     .12       0  4783.5     .05       0
  4984.9     .03       0  5060.2     .05       0  5132.2     .12       0
  5173.2     .05       0
Bank Sta=4984.9,5060.2
XS Rating Curve= 0 ,0
Exp/Cntr=0.3,0.1

Type RM Length L Ch R = 1 ,56000   ,553,553,553
BEGIN DESCRIPTION:
SAN FERNANDO CREEK 112.0
END DESCRIPTION:
XS GIS Cut Line= 3
       2758405.7     10260153.13      2758138.58     10259744.49
      2758105.68      10259553.1
#Sta/Elev= 30
  4511.8 1204.36  4540.5 1202.13  4555.6 1199.91  4623.1 1194.63  4649.1 1193.19
  4664.2 1191.47  4746.7 1187.49  4772.8 1187.13  4778.7 1186.34  4814.9 1186.68
  4822.4 1185.85  4845.2 1181.22  4858.3 1179.68    4930 1175.95  4937.2 1174.01
  4938.7 1173.01    5011 1173.01  5012.5 1174.01  5030.5 1178.79  5052.1  1186.1
  5082.6 1189.14  5092.7 1191.05  5101.7 1194.82  5106.8 1194.36    5113 1197.81
  5123.2 1201.74  5143.5 1208.36  5147.7 1208.98  5161.7 1211.91  5194.2 1217.03
#Mann= 7 ,-1 , 0
  4511.8     .05       0  4623.1     .12       0  4746.7     .05       0
  4937.2     .03       0  5012.5     .05       0  5030.5     .12       0
  5147.7     .05       0
Bank Sta=4937.2,5012.5
XS Rating Curve= 0 ,0
Exp/Cntr=0.3,0.1

Type RM Length L Ch R = 1 ,55447   ,679,679,679
BEGIN DESCRIPTION:
Mapping XS 32c739ed
END DESCRIPTION:
XS GIS Cut Line= 3
      2758515.77     10260211.51      2758700.22     10259766.66
      2758591.93      10259116.9
#Sta/Elev= 30
  4389.2 1209.11  4615.6 1198.37  4657.9 1194.46  4663.3 1195.99  4687.2  1191.3
  4804.6 1185.37  4863.8 1182.75  4884.5 1178.04  4945.3 1174.26  4947.6  1172.9
  4949.1  1171.9  5022.9  1172.9  5050.6 1175.43  5056.9 1178.65  5077.1 1183.12
  5106.9 1185.33    5138 1191.67  5167.7 1194.56  5172.8 1196.53  5198.8 1199.13
    5229  1199.8  5239.3 1200.57  5289.4 1196.93  5294.4 1198.99  5340.7  1201.5
    5361 1206.53    5432 1202.19  5471.8 1208.35  5476.9 1207.41  5529.5 1213.68
#Mann= 6 ,-1 , 0
  4389.2     .12       0  4804.6     .05       0  4947.6     .03       0
  5022.9     .05       0  5050.6     .12       0    5229     .05       0
Bank Sta=4947.6,5022.9
XS Rating Curve= 0 ,0
Exp/Cntr=0.3,0.1

Type RM Length L Ch R = 1 ,54768   ,392,392,392
BEGIN DESCRIPTION:
Mapping XS e5447084
END DESCRIPTION:
XS GIS Cut Line= 2
      2759416.37      10260254.9      2759307.87     10259083.11
#Sta/Elev= 30
  4349.9 1223.11  4492.3 1211.19  4552.5 1203.34  4612.8 1198.22    4663 1192.27
    4781 1182.23  4833.7 1174.67    4894 1174.84  4956.1 1172.21  4957.6 1171.21
  5031.3 1171.21  5032.8 1172.21  5044.6 1178.52  5054.7 1180.73  5082.8 1181.93
    5125 1185.29  5185.2 1194.62  5215.4 1190.53  5235.5 1194.71  5254.4 1200.54
  5274.9 1204.37  5305.8    1206    5356 1211.26  5384.4 1211.67  5389.4 1209.42
  5406.2 1210.98  5456.4 1217.57  5493.8 1225.14  5498.9 1223.26  5526.7 1230.69
#Mann= 6 ,-1 , 0
  4349.9     .12       0    4781     .05       0  4956.1     .03       0
  5032.8     .05       0  5082.8     .12       0  5254.4     .05       0
Bank Sta=4956.1,5032.8
XS Rating Curve= 0 ,0
Exp/Cntr=0.3,0.1

Type RM Length L Ch R = 1 ,54376   ,675,675,675
BEGIN DESCRIPTION:
Mapping XS c4b529d8
END DESCRIPTION:
XS GIS Cut Line= 3
      2759681.42     10260363.55      2759753.82     10259829.58
      2759735.72     10259150.78
#Sta/Elev= 30
  4247.4 1221.71  4308.4 1222.77  4379.9 1222.27  4429.5 1218.81  4459.8 1215.04
    4465 1213.37  4479.9 1212.55  4537.5 1204.93  4615.1 1197.66  4687.6 1189.09
  4778.5 1181.09  4812.7 1179.53  4852.8 1173.28  4872.8 1172.17  4952.8 1173.53
  4962.8 1173.41  4964.5 1171.97    4966 1170.97  5039.7 1170.97  5041.2 1171.97
  5042.8 1178.62  5102.8 1182.49  5142.9 1191.64  5222.9 1205.22  5272.9 1211.57
  5278.5  1213.2  5283.5 1212.26  5302.9 1214.52  5372.9 1228.68  5465.3 1236.08
#Mann= 5 ,-1 , 0
  4247.4     .05       0  4379.9     .12       0  4778.5     .05       0
  4964.5     .03       0  5041.2     .12       0
Bank Sta=4964.5,5041.2
XS Rating Curve= 0 ,0
Exp/Cntr=0.3,0.1

Type RM Length L Ch R = 1 ,53701   ,891,891,891
BEGIN DESCRIPTION:
Mapping XS 894921cd
END DESCRIPTION:
XS GIS Cut Line= 3
      2760441.69     10260499.32      2760387.39     10259594.26
      2760261.03     10259106.86
#Sta/Elev= 30
    4289  1212.5  4295.2 1211.21  4315.3 1212.12  4485.6 1209.88  4575.7 1201.91
  4826.2 1186.39  4866.2  1179.9  4966.4 1171.96  4968.1 1170.26  4969.6 1169.26
  5044.8 1170.26  5046.6 1171.69  5076.6 1170.85  5106.7 1173.43  5116.7 1171.03
  5166.8 1173.77  5186.8 1175.76  5193.8 1178.29  5248.5 1178.96  5263.1 1180.47
  5269.2 1183.23  5303.7 1184.22  5320.8 1187.89  5351.8 1190.88  5384.9 1197.18
  5393.2  1196.1  5425.5 1198.32  5658.6 1228.94  5663.8 1227.79  5699.2 1233.09
#Mann= 3 ,-1 , 0
    4289     .05       0  4968.1     .03       0  5044.8     .05       0
Bank Sta=4968.1,5044.8
XS Rating Curve= 0 ,0
Exp/Cntr=0.3,0.1

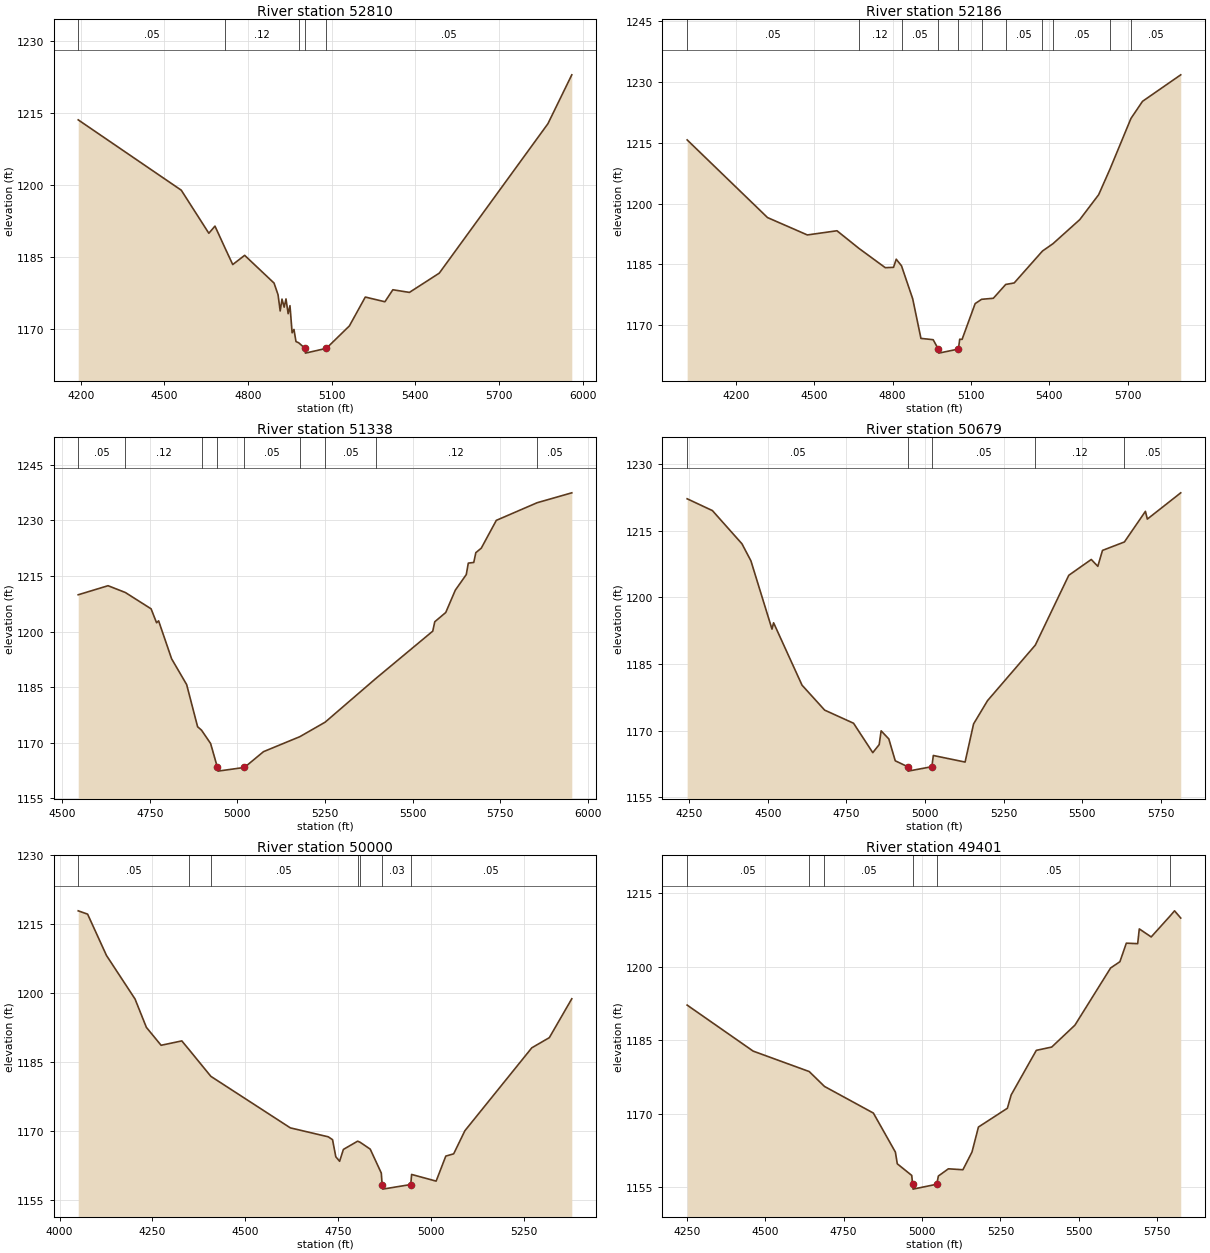
Type RM Length L Ch R = 1 ,52810   ,624,624,624
BEGIN DESCRIPTION:
Mapping XS b6291df4
END DESCRIPTION:
XS GIS Cut Line= 3
      2761880.82     10260218.79       2760975.7     10259449.44
      2760486.99     10259132.69
#Sta/Elev= 30
  4190.7 1213.54  4560.3 1198.89  4659.2 1189.92  4681.2 1191.41  4717.7 1186.79
  4744.9  1183.4  4787.7 1185.32  4893.1 1179.54  4907.4 1177.12  4915.1 1173.73
  4921.6  1176.2  4929.4 1174.52  4935.9 1176.24  4943.7 1173.16  4950.2 1174.84
  4957.9 1169.19  4964.5 1169.88  4971.8 1167.35  4981.4 1167.11  5004.1 1165.95
  5005.6 1164.95  5080.8 1165.95  5163.3 1170.62  5220.4 1176.63  5290.7 1175.65
  5319.2 1178.15  5378.6  1177.6  5485.7 1181.61  5875.3 1212.73    5961 1222.92
#Mann= 5 ,-1 , 0
  4190.7     .05       0  4717.7     .12       0  4981.4     .05       0
  5004.1     .03       0  5080.8     .05       0
Bank Sta=5004.1,5080.8
XS Rating Curve= 0 ,0
Exp/Cntr=0.3,0.1

Type RM Length L Ch R = 1 ,52186   ,848,848,848
BEGIN DESCRIPTION:
Mapping XS e9ec96aa
END DESCRIPTION:
XS GIS Cut Line= 4
      2762020.55     10259875.19      2761673.31     10259245.83
      2761130.78     10259072.22      2760555.65     10258898.59
#Sta/Elev= 30
  4013.4 1215.67    4321 1196.54  4473.4 1192.26  4586.8 1193.29  4671.3 1188.93
  4771.7  1184.2  4803.2 1184.28  4813.7 1186.28  4833.8 1184.66  4876.7 1176.53
  4908.2 1166.78  4954.9 1166.46  4974.8 1164.15  4976.3 1163.15  5051.6 1164.15
  5056.6 1166.57  5065.7 1166.54  5115.7 1175.35  5140.6 1176.41  5185.3 1176.66
  5232.6 1180.06  5265.2 1180.44  5373.4  1188.3  5413.5  1190.1  5516.1 1196.03
  5588.4 1202.17  5631.4 1208.42  5712.1 1220.96  5756.3 1225.17  5902.6  1231.7
#Mann= 11 ,-1 , 0
  4013.4     .05       0  4671.3     .12       0  4833.8     .05       0
  4974.8     .03       0  5051.6     .05       0  5140.6     .12       0
  5232.6     .05       0  5373.4     .12       0  5413.5     .05       0
  5631.4     .12       0  5712.1     .05       0
Bank Sta=4974.8,5051.6
XS Rating Curve= 0 ,0
Exp/Cntr=0.3,0.1

Type RM Length L Ch R = 1 ,51338   ,659,659,659
BEGIN DESCRIPTION:
Mapping XS f397c732
END DESCRIPTION:
XS GIS Cut Line= 2
       2761521.4     10258193.32      2760307.23     10258908.81
#Sta/Elev= 30
  4545.4 1209.92  4630.6 1212.36    4680 1210.53  4753.5 1206.12  4769.1 1202.36
  4774.9 1202.89    4812 1192.65    4855 1185.68  4886.3  1174.3  4897.4 1173.38
  4923.4 1169.78  4942.9 1163.32  4944.4 1162.32  5020.1 1163.32  5074.4 1167.57
  5178.5 1171.63  5250.4 1175.53  5394.3 1187.25  5557.7  1200.1  5563.5 1202.64
  5594.8 1205.13  5622.1 1211.16  5653.4 1215.36  5659.2 1218.46  5674.8 1218.64
  5680.7 1221.28  5696.3  1222.5  5739.2    1230  5855.8 1234.76  5954.7 1237.43
#Mann= 9 ,-1 , 0
  4545.4     .05       0    4680     .12       0  4897.4     .05       0
  4942.9     .03       0  5020.1     .05       0  5178.5     .12       0
  5250.4     .05       0  5394.3     .12       0  5855.8     .05       0
Bank Sta=4942.9,5020.1
XS Rating Curve= 0 ,0
Exp/Cntr=0.3,0.1

Type RM Length L Ch R = 1 ,50679   ,679,679,679
BEGIN DESCRIPTION:
Mapping XS 187fd0b0
END DESCRIPTION:
XS GIS Cut Line= 3
      2761274.42     10257883.62      2760613.66      10258019.4
      2760097.77      10258752.5
#Sta/Elev= 30
  4242.9  1222.2  4323.3 1219.54  4417.3 1212.07  4445.8 1208.24  4512.9 1192.86
    4518 1194.29  4608.5 1180.25  4680.6 1174.63  4772.5 1171.68  4833.7 1165.06
  4854.1 1166.87  4860.3 1169.97  4884.8 1168.14  4905.2 1163.23  4944.6  1161.9
  4946.1  1160.9  5021.8  1161.9  5026.4 1164.42  5127.5 1162.94  5154.5 1171.52
  5198.9 1176.76    5351 1189.26  5457.6 1204.98  5529.1 1208.54    5550    1207
  5564.8 1210.58  5634.6 1212.48  5701.5 1219.37  5707.6 1217.63  5813.9 1223.54
#Mann= 5 ,-1 , 0
  4242.9     .05       0  4944.6     .03       0  5021.8     .05       0
    5351     .12       0  5634.6     .05       0
Bank Sta=4944.6,5021.8
XS Rating Curve= 0 ,0
Exp/Cntr=0.3,0.1

Type RM Length L Ch R = 1 ,50000   ,599,599,599
BEGIN DESCRIPTION:
SAN FERNANDO CREEK 100.0
END DESCRIPTION:
XS GIS Cut Line= 3
      2761205.66     10257753.11      2760274.69     10257564.89
      2759905.69     10257653.11
#Sta/Elev= 30
  4050.2 1217.95  4075.5 1217.23  4126.3 1208.25  4203.2 1198.79  4233.8 1192.62
  4273.4 1188.73  4329.2 1189.68  4347.8 1187.87  4407.4 1181.98  4621.5 1170.78
  4723.5 1168.84  4735.1 1168.22  4743.9  1164.5  4754.1 1163.52  4764.3  1166.1
  4802.7 1167.89  4809.4 1167.65  4836.6 1166.16  4866.4 1160.96  4868.6 1158.47
  4870.1 1157.47  4945.8 1158.47    4948 1160.66  5014.1 1159.21  5040.1 1164.65
  5061.3 1165.14  5091.5 1170.16  5271.7 1188.18  5318.9 1190.39  5379.4 1198.84
#Mann= 7 ,-1 , 0
  4050.2     .05       0  4347.8     .12       0  4407.4     .05       0
  4802.7     .12       0  4809.4     .05       0  4868.6     .03       0
  4945.8     .05       0
Bank Sta=4868.6,4945.8
XS Rating Curve= 0 ,0
Exp/Cntr=0.3,0.1

Type RM Length L Ch R = 1 ,49401   ,690,690,690
BEGIN DESCRIPTION:
Mapping XS 052377fe
END DESCRIPTION:
XS GIS Cut Line= 3
      2761129.55     10257304.37      2760324.03     10256951.39
      2759646.49     10256797.81
#Sta/Elev= 30
  4250.9 1192.16  4461.5 1182.78  4640.2 1178.62  4688.8 1175.59  4844.8 1170.16
    4915 1162.21  4921.1 1159.82  4967.2 1157.45  4969.8 1155.66  4971.3 1154.66
  5047.1 1155.66  5052.1 1157.33  5084.1  1158.8  5130.4 1158.61  5159.4 1162.23
  5179.9 1167.31  5272.2 1171.14  5284.3 1173.86  5364.5 1182.94  5413.6 1183.61
  5487.6 1188.07  5601.5 1199.73  5631.1    1201  5651.6 1204.78  5687.8 1204.68
  5692.9 1207.69  5730.9 1206.05  5791.2 1210.32  5805.4 1211.37  5825.1  1209.9
#Mann= 6 ,-1 , 0
  4250.9     .05       0  4640.2     .12       0  4688.8     .05       0
  4969.8     .03       0  5047.1     .05       0  5791.2     .12       0
Bank Sta=4969.8,5047.1
XS Rating Curve= 0 ,0
Exp/Cntr=0.3,0.1

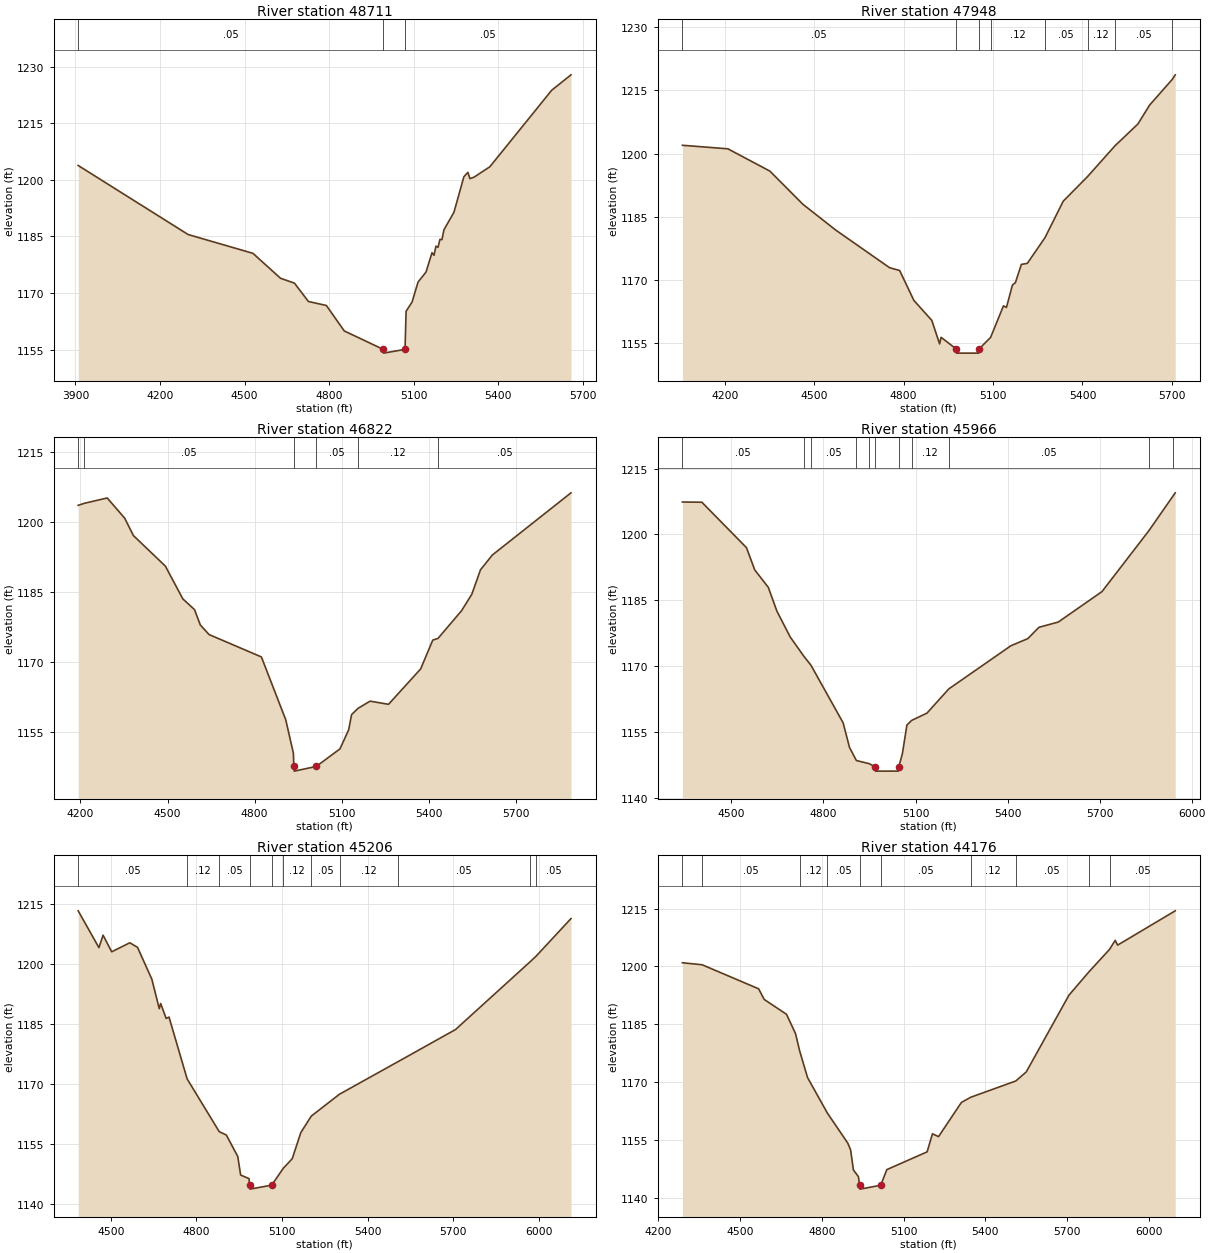
Type RM Length L Ch R = 1 ,48711   ,763,763,763
BEGIN DESCRIPTION:
Mapping XS b7f61c94
END DESCRIPTION:
XS GIS Cut Line= 3
      2761401.07     10257231.94      2761039.05     10256734.17
      2760233.74      10255937.9
#Sta/Elev= 30
  3909.8 1203.85  4299.7 1185.52  4529.6 1180.53  4627.5 1173.91  4676.9 1172.62
  4726.5 1167.74  4790.1 1166.69  4853.7 1159.92  4991.8 1155.04  4993.3 1154.04
  5069.1 1155.04  5072.9 1165.15  5094.1  1167.6  5115.3  1172.9  5143.6 1175.56
  5164.8  1180.7  5171.9 1180.01  5178.9 1182.43  5186.1 1182.11  5193.1 1184.25
  5200.2 1184.16  5207.2 1186.79  5242.6 1191.42  5277.9 1200.86  5292.1 1202.02
  5299.2 1200.36  5313.3 1200.72  5369.9  1203.5  5589.1  1223.8  5657.8 1227.91
#Mann= 3 ,-1 , 0
  3909.8     .05       0  4991.8     .03       0  5069.1     .05       0
Bank Sta=4991.8,5069.1
XS Rating Curve= 0 ,0
Exp/Cntr=0.3,0.1

Type RM Length L Ch R = 1 ,47948   ,1126,1126,1126
BEGIN DESCRIPTION:
Mapping XS bbd0ff88
END DESCRIPTION:
XS GIS Cut Line= 3
      2761518.75     10257204.78      2761437.29     10256480.74
      2761392.05     10255557.85
#Sta/Elev= 30
  4058.4 1201.97    4211 1201.13  4351.9 1195.84  4462.6 1187.98    4573 1181.85
    4753 1172.96    4787 1172.28  4834.7 1165.19  4894.8 1160.46  4920.9 1154.89
  4925.9 1156.45  4976.3  1153.7  4977.8  1152.7  5052.1  1152.7  5053.6  1153.7
    5092 1156.44  5135.1 1163.91  5145.1 1163.53  5165.1 1168.84  5175.1 1169.41
  5195.1 1173.73  5215.1 1173.98  5274.4 1180.08  5335.4 1188.71    5417 1194.55
  5509.2 1201.86  5585.6 1206.99  5625.6 1211.54  5701.5 1217.62    5711 1218.67
#Mann= 8 ,-1 , 0
  4058.4     .05       0  4976.3     .05       0  5053.6     .05       0
    5092     .12       0  5274.4     .05       0    5417     .12       0
  5509.2     .05       0  5701.5     .12       0
Bank Sta=4976.3,5053.6
XS Rating Curve= 0 ,0
Exp/Cntr=0.3,0.1

Type RM Length L Ch R = 1 ,46822   ,856,856,856
BEGIN DESCRIPTION:
Mapping XS 6f7dbd37
END DESCRIPTION:
XS GIS Cut Line= 3
      2762577.71     10257032.85      2762514.35     10256073.45
      2762225.48      10255396.4
#Sta/Elev= 30
  4192.1  1203.6  4213.1 1204.03  4292.1 1205.18  4352.2 1200.86  4382.3 1197.13
  4492.5 1190.58  4552.6 1183.56  4592.7 1181.28  4612.8 1177.98  4642.8 1175.93
  4823.2 1171.13  4907.1 1157.67  4933.5 1150.49  4934.9 1147.67  4936.4 1146.67
  5012.2 1147.67  5093.8 1151.43  5123.9 1155.52  5133.9 1158.78  5156.2 1160.12
  5197.5 1161.66  5261.1 1160.98  5371.8 1168.56  5413.6 1174.74  5431.5 1175.09
  5512.7 1181.03    5548 1184.55    5578  1189.8  5618.8 1192.96  5889.7 1206.28
#Mann= 6 ,-1 , 0
  4192.1     .12       0  4213.1     .05       0  4934.9     .03       0
  5012.2     .05       0  5156.2     .12       0  5431.5     .05       0
Bank Sta=4934.9,5012.2
XS Rating Curve= 0 ,0
Exp/Cntr=0.3,0.1

Type RM Length L Ch R = 1 ,45966   ,760,760,760
BEGIN DESCRIPTION:
Mapping XS 780ce20d
END DESCRIPTION:
XS GIS Cut Line= 3
      2763727.14     10256091.52      2762921.64     10255521.34
      2762360.56      10255258.9
#Sta/Elev= 30
  4340.2 1207.38  4403.7 1207.33    4549    1197    4576 1191.94  4620.3 1187.96
  4648.3 1182.55  4691.7 1176.67  4736.3 1172.28  4759.2 1170.26    4864 1157.17
  4884.9 1151.56  4907.3 1148.58  4948.6 1147.88    4968 1147.17  4969.5 1146.17
    5044 1146.17  5045.5 1147.17  5057.2 1150.12    5072 1156.66  5087.3  1157.7
  5137.3 1159.36  5208.7 1164.88    5411 1174.69  5466.1 1176.31  5502.3 1178.88
  5565.4 1180.08  5707.9 1187.01  5860.5 1200.84  5938.2 1208.63  5946.5 1209.47
#Mann= 11 ,-1 , 0
  4340.2     .05       0  4736.3     .12       0  4759.2     .05       0
  4907.3     .12       0  4948.6     .05       0    4968     .05       0
  5045.5     .05       0  5087.3     .12       0  5208.7     .05       0
  5860.5     .12       0  5938.2     .05       0
Bank Sta=4968,5045.5
XS Rating Curve= 0 ,0
Exp/Cntr=0.3,0.1

Type RM Length L Ch R = 1 ,45206   ,1030,1030,1030
BEGIN DESCRIPTION:
Mapping XS 312e0ef8
END DESCRIPTION:
XS GIS Cut Line= 2
      2764152.62     10255105.01      2762432.92     10254942.09
#Sta/Elev= 30
  4385.7 1213.23  4458.4 1204.05    4473 1207.15  4503.2 1203.01  4566.6 1205.26
  4593.6 1204.13  4643.8 1196.19  4669.9 1188.83  4674.9 1190.11    4694 1186.39
  4704.1 1186.72  4767.6  1171.3  4880.1 1158.14  4904.9 1157.31  4945.1 1151.94
  4955.2 1147.31  4984.6 1146.42  4986.7  1144.8  4988.2  1143.8  5064.2  1144.8
  5104.1 1148.95    5136 1151.39  5166.1 1157.91  5202.9 1162.03  5301.7 1167.48
  5508.3 1175.66  5708.5 1183.62  5968.7 1200.45  5991.7 1201.99  6113.1  1211.3
#Mann= 11 ,-1 , 0
  4385.7     .05       0  4767.6     .12       0  4880.1     .05       0
  4986.7     .05       0  5064.2     .05       0  5104.1     .12       0
  5202.9     .05       0  5301.7     .12       0  5508.3     .05       0
  5968.7     .12       0  5991.7     .05       0
Bank Sta=4986.7,5064.2
XS Rating Curve= 0 ,0
Exp/Cntr=0.3,0.1

Type RM Length L Ch R = 1 ,44176   ,519,519,519
BEGIN DESCRIPTION:
Mapping XS 8f6171c5
END DESCRIPTION:
XS GIS Cut Line= 3
      2763899.16     10254000.79       2763021.2     10254190.86
      2762206.64     10254598.14
#Sta/Elev= 30
  4288.4 1200.97  4360.7 1200.45  4568.2 1194.22  4588.7 1191.46  4670.5 1187.61
  4703.7 1182.61  4718.8 1178.13  4747.8 1171.21  4820.8 1161.98  4895.6  1154.2
  4905.9 1152.46  4916.1 1147.26  4934.4 1145.54  4938.7 1143.29  4940.2 1142.29
  5016.2 1143.29  5038.9 1147.35  5186.7 1151.95  5206.3 1156.63  5228.6  1155.9
  5312.5 1164.75  5346.2 1166.09  5512.1 1170.32  5550.6 1172.67  5707.2 1192.55
  5779.9 1198.55  5856.3 1204.43  5877.1 1206.77    5886 1205.54  6097.4 1214.43
#Mann= 10 ,-1 , 0
  4288.4     .12       0  4360.7     .05       0  4718.8     .12       0
  4820.8     .05       0  4938.7     .05       0  5016.2     .05       0
  5346.2     .12       0  5512.1     .05       0  5779.9     .12       0
  5856.3     .05       0
Bank Sta=4938.7,5016.2
XS Rating Curve= 0 ,0
Exp/Cntr=0.3,0.1

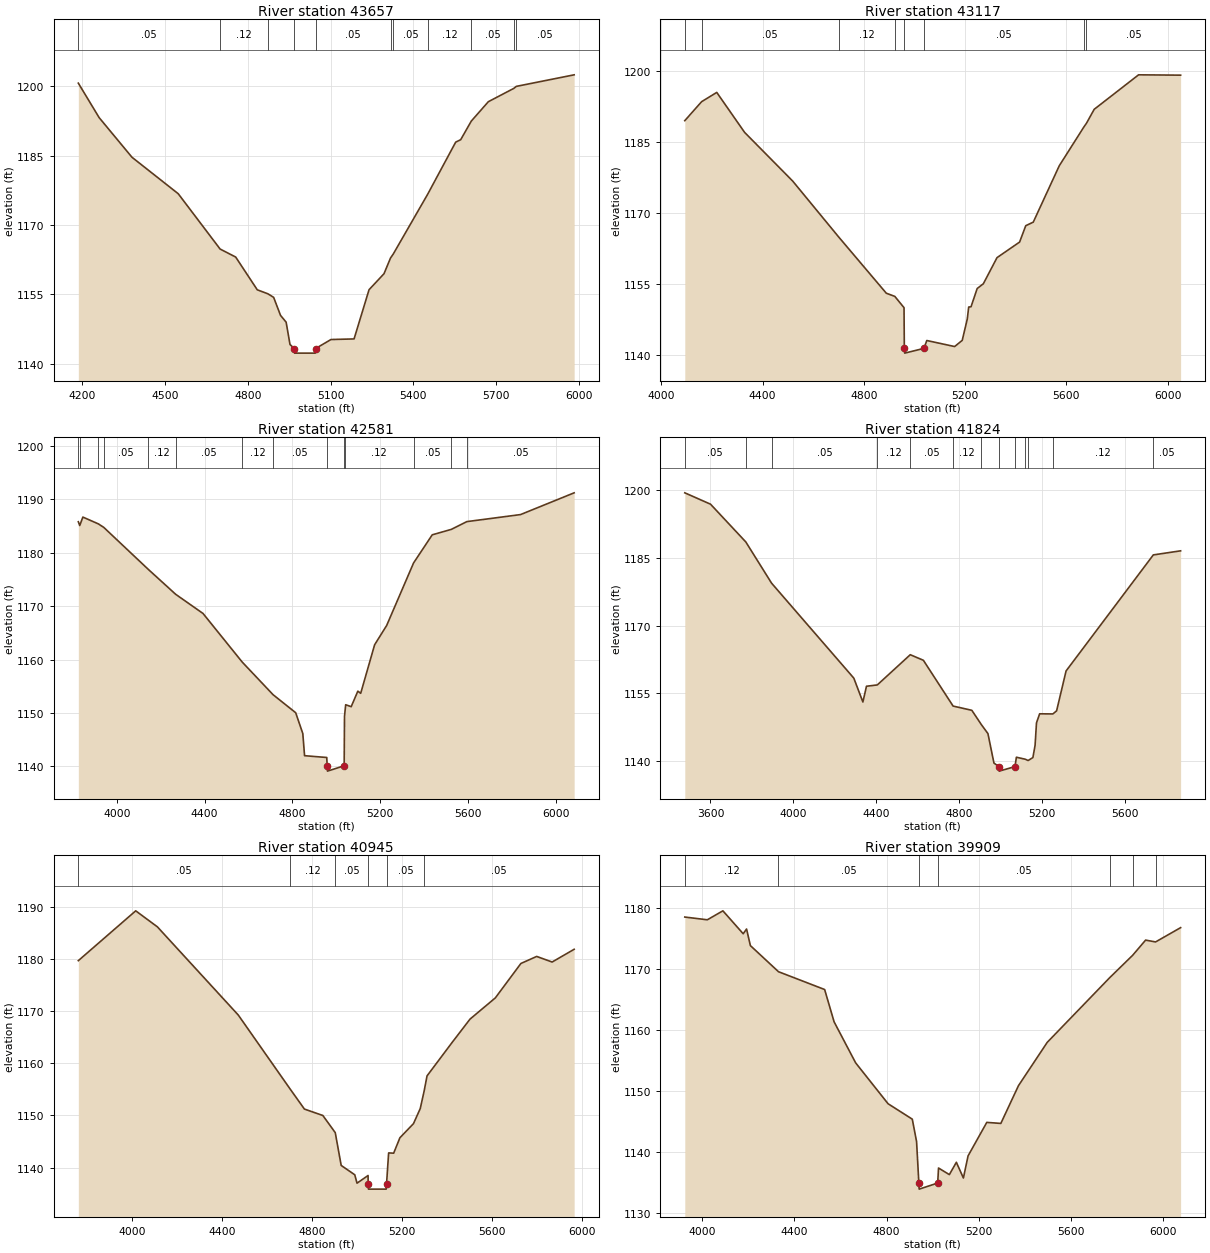
Type RM Length L Ch R = 1 ,43657   ,540,540,540
BEGIN DESCRIPTION:
Mapping XS a638c522
END DESCRIPTION:
XS GIS Cut Line= 3
      2763727.17      10253575.4      2762595.81     10253774.52
      2761999.59     10254027.46
#Sta/Elev= 30
  4186.1 1200.66  4261.6  1193.2  4380.5 1184.64    4548 1176.76  4699.8  1164.8
  4756.2 1163.07  4834.4 1155.99    4873 1155.12  4893.7 1154.36  4918.7 1150.46
    4939 1148.99    4953 1144.17  4968.4  1143.3  4969.9  1142.3  5044.5  1142.3
    5046  1143.3  5101.4 1145.24  5185.1 1145.37  5239.4 1156.01  5293.6 1159.47
  5317.2 1162.86  5327.1 1163.72    5452 1176.67  5553.3 1187.91  5571.5 1188.44
  5609.7 1192.45  5671.6 1196.65  5763.6 1199.52  5772.9 1199.96  5982.5 1202.46
#Mann= 11 ,-1 , 0
  4186.1     .05       0  4699.8     .12       0    4873     .05       0
  4968.4     .03       0    5046     .05       0  5317.2     .12       0
  5327.1     .05       0    5452     .12       0  5609.7     .05       0
  5763.6     .12       0  5772.9     .05       0
Bank Sta=4968.4,5046
XS Rating Curve= 0 ,0
Exp/Cntr=0.3,0.1

Type RM Length L Ch R = 1 ,43117   ,536,536,536
BEGIN DESCRIPTION:
Mapping XS 96ef265e
END DESCRIPTION:
XS GIS Cut Line= 3
      2763681.94     10253213.36      2762559.61     10253195.26
      2761781.21       10253503.
#Sta/Elev= 30
  4092.2 1189.55  4158.6 1193.55  4218.5 1195.51  4328.5 1187.08  4518.5 1176.81
  4700.9 1164.97  4888.6 1153.14  4922.2 1152.47  4958.6 1150.09  4959.8  1141.5
  4961.3  1140.5  5037.4  1141.5  5048.6 1143.16  5158.6 1141.89  5188.6 1143.19
  5208.6  1147.7  5214.1 1150.22  5223.4 1150.28  5247.7 1154.13  5272.1 1155.14
  5326.1 1160.65  5415.3 1163.93  5439.7 1167.39  5469.4 1168.14  5572.2 1180.04
  5669.4 1188.22  5679.5 1188.99  5710.1 1191.94  5885.6 1199.22  6051.7 1199.15
#Mann= 8 ,-1 , 0
  4092.2     .12       0  4158.6     .05       0  4700.9     .12       0
  4922.2     .05       0  4959.8     .05       0  5037.4     .05       0
  5669.4     .12       0  5679.5     .05       0
Bank Sta=4959.8,5037.4
XS Rating Curve= 0 ,0
Exp/Cntr=0.3,0.1

Type RM Length L Ch R = 1 ,42581   ,757,757,757
BEGIN DESCRIPTION:
Mapping XS 5393f874
END DESCRIPTION:
XS GIS Cut Line= 4
       2763627.6     10253068.54      2762894.49     10252679.36
      2762125.16     10252797.02      2761763.77     10253339.11
#Sta/Elev= 30
  3824.4 1185.81  3830.8  1185.1  3845.1 1186.68  3915.5 1185.41  3940.1 1184.76
  4143.6 1176.88    4268 1172.23  4392.7 1168.64  4571.4 1159.54  4711.9 1153.44
  4815.1 1150.06  4847.5 1146.16  4855.5 1142.02  4956.7 1141.68  4958.4 1140.13
  4959.9 1139.13    5036 1140.13  5037.5 1149.37  5042.9 1151.56    5068 1151.19
  5098.3  1154.1  5111.3 1153.69  5174.8 1162.78  5229.8  1166.4  5352.4  1178.1
  5437.4 1183.36  5524.4 1184.38  5595.1 1185.83    5840 1187.15  6084.2 1191.22
#Mann= 14 ,-1 , 0
  3824.4     .12       0  3830.8     .05       0  3915.5     .12       0
  3940.1     .05       0  4143.6     .12       0    4268     .05       0
  4571.4     .12       0  4711.9     .05       0  4958.4     .03       0
    5036     .05       0  5037.5     .12       0  5352.4     .05       0
  5524.4     .12       0  5595.1     .05       0
Bank Sta=4958.4,5036
XS Rating Curve= 0 ,0
Exp/Cntr=0.3,0.1

Type RM Length L Ch R = 1 ,41824   ,879,879,879
BEGIN DESCRIPTION:
Mapping XS 8c89f15a
END DESCRIPTION:
XS GIS Cut Line= 4
      2764197.79     10252235.86      2762794.93     10251973.38
      2762405.74      10252154.4      2762116.13     10252606.93
#Sta/Elev= 30
  3476.2 1199.35  3600.4 1196.84  3770.8 1188.49  3895.2 1179.38  4292.2 1158.39
    4336 1153.12  4353.3  1156.6  4405.5 1156.89  4564.7 1163.57    4628 1162.34
  4771.5 1152.22  4861.9 1151.28  4907.8 1148.13  4939.7 1146.13  4968.7 1139.62
  4992.5 1138.84    4994 1137.84  5070.1 1138.84  5077.1 1140.91  5120.1 1140.47
  5133.6 1140.18  5156.7 1140.84  5167.3 1143.56  5174.1 1148.51  5189.3 1150.51
  5253.1 1150.48  5271.2 1151.17  5316.9 1159.98  5738.1 1185.63  5869.9 1186.53
#Mann= 13 ,-1 , 0
  3476.2     .05       0  3770.8     .12       0  3895.2     .05       0
  4405.5     .12       0  4564.7     .05       0  4771.5     .12       0
  4907.8     .05       0  4992.5     .05       0  5070.1     .05       0
  5120.1     .12       0  5133.6     .05       0  5253.1     .12       0
  5738.1     .05       0
Bank Sta=4992.5,5070.1
XS Rating Curve= 0 ,0
Exp/Cntr=0.3,0.1

Type RM Length L Ch R = 1 ,40945   ,1036,1036,1036
BEGIN DESCRIPTION:
Mapping XS 7984f833
END DESCRIPTION:
XS GIS Cut Line= 4
      2764025.89     10251475.59      2762912.59     10251222.16
      2762333.33     10251167.85      2761862.72      10251068.3
#Sta/Elev= 30
  3759.8 1179.64    4015 1189.19  4111.4 1186.12    4471 1169.22  4701.6 1155.04
  4765.1  1151.2  4847.1 1149.97  4902.2 1146.68  4928.6  1140.4  4988.9 1138.61
  4998.9    1137  5048.1 1138.47  5048.5 1136.86    5050 1135.86  5128.7 1135.86
  5130.2 1136.86  5139.5  1142.8  5161.9 1142.75  5189.7 1145.71    5250 1148.41
  5280.1  1151.3  5297.3 1154.64  5310.3 1157.56  5420.8 1163.91  5501.4 1168.44
  5613.8  1172.5  5727.6  1179.1  5797.8 1180.45  5866.5 1179.38  5964.4 1181.82
#Mann= 6 ,-1 , 0
  3759.8     .05       0  4701.6     .12       0  4902.2     .05       0
  5048.5     .05       0  5130.2     .05       0  5297.3     .05       0
Bank Sta=5048.5,5130.2
XS Rating Curve= 0 ,0
Exp/Cntr=0.3,0.1

Type RM Length L Ch R = 1 ,39909   ,736,736,736
BEGIN DESCRIPTION:
Mapping XS d2c68b35
END DESCRIPTION:
XS GIS Cut Line= 4
      2764048.82     10250561.53      2763172.12     10250257.72
      2762677.32     10250170.92      2761965.61     10250058.09
#Sta/Elev= 30
  3924.8 1178.44  4022.5 1177.99  4090.1 1179.46  4178.2  1175.7  4192.7 1176.48
  4209.3 1173.76  4331.2 1169.48  4531.4 1166.56  4572.5 1161.26  4665.9 1154.54
  4806.5 1147.84  4911.6 1145.31  4930.2 1141.64  4940.1 1134.84  4941.6 1133.84
  5021.9 1134.84  5025.4  1137.3  5072.4 1136.22  5102.8 1138.24  5133.3 1135.66
  5153.6 1139.29  5234.8 1144.78  5295.7 1144.61  5372.4 1150.81    5497  1157.9
  5768.2 1168.51  5867.5 1172.17  5923.7 1174.66  5966.9 1174.36  6075.6  1176.7
#Mann= 7 ,-1 , 0
  3924.8     .12       0  4331.2     .05       0  4940.1     .05       0
  5021.9     .05       0  5768.2     .12       0  5867.5     .05       0
  5966.9     .12       0
Bank Sta=4940.1,5021.9
XS Rating Curve= 0 ,0
Exp/Cntr=0.3,0.1