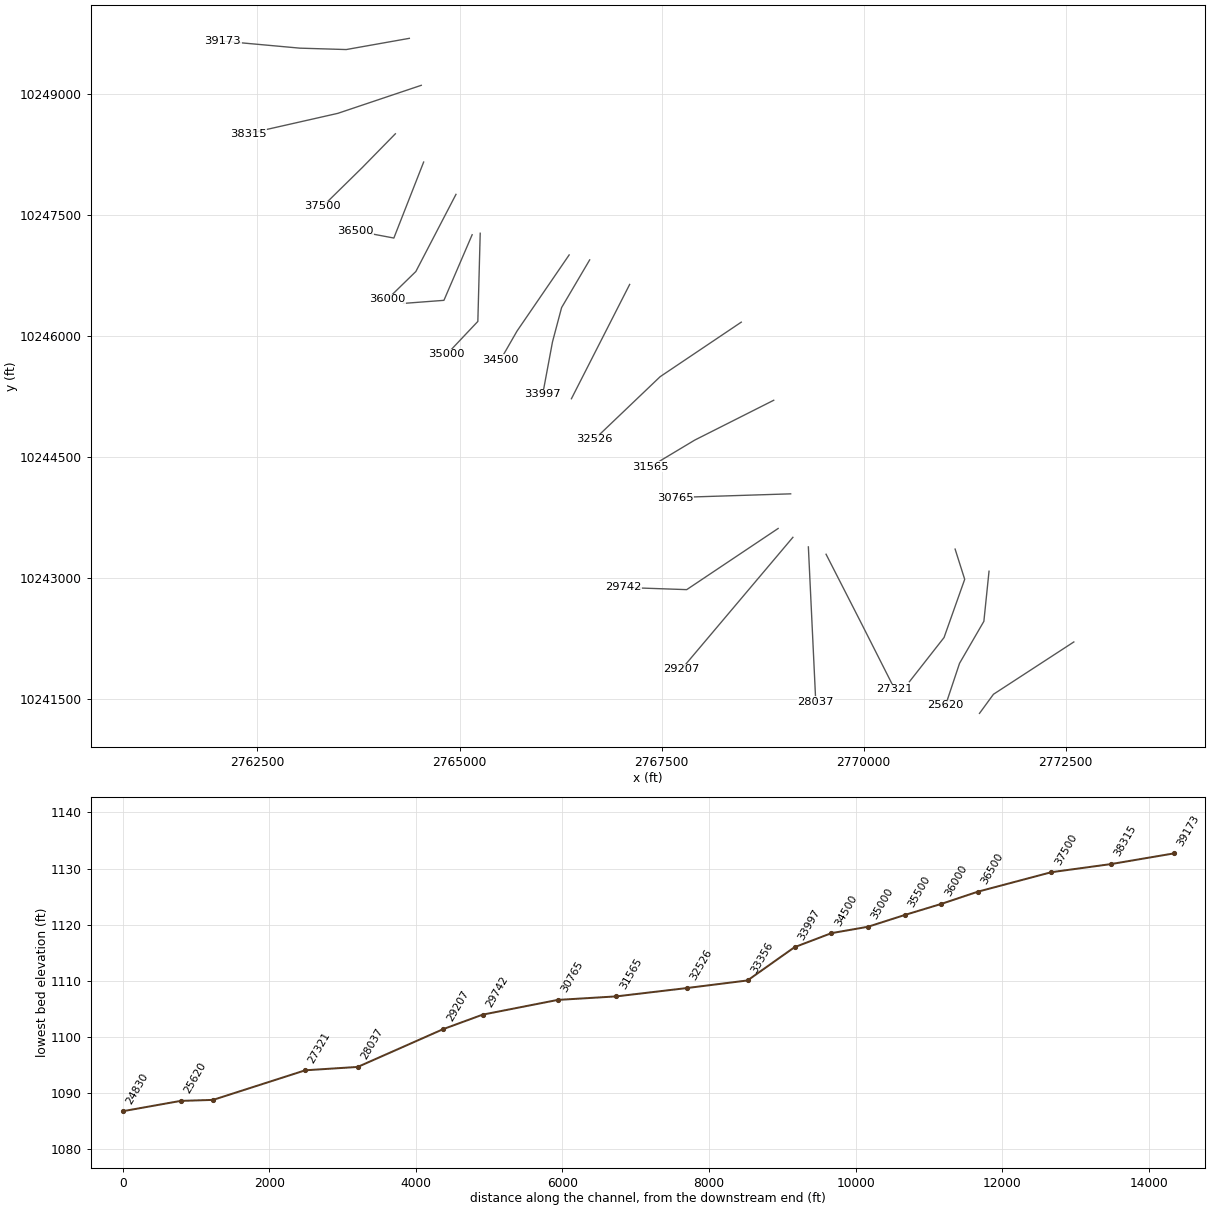
HEC-RAS study SAN FERNANDO CREEK.prj: SAN FERNANDO CREEK Base Level Engineering

--- SAN FERNANDO CREEK.g01 (geometry) --- (continued)

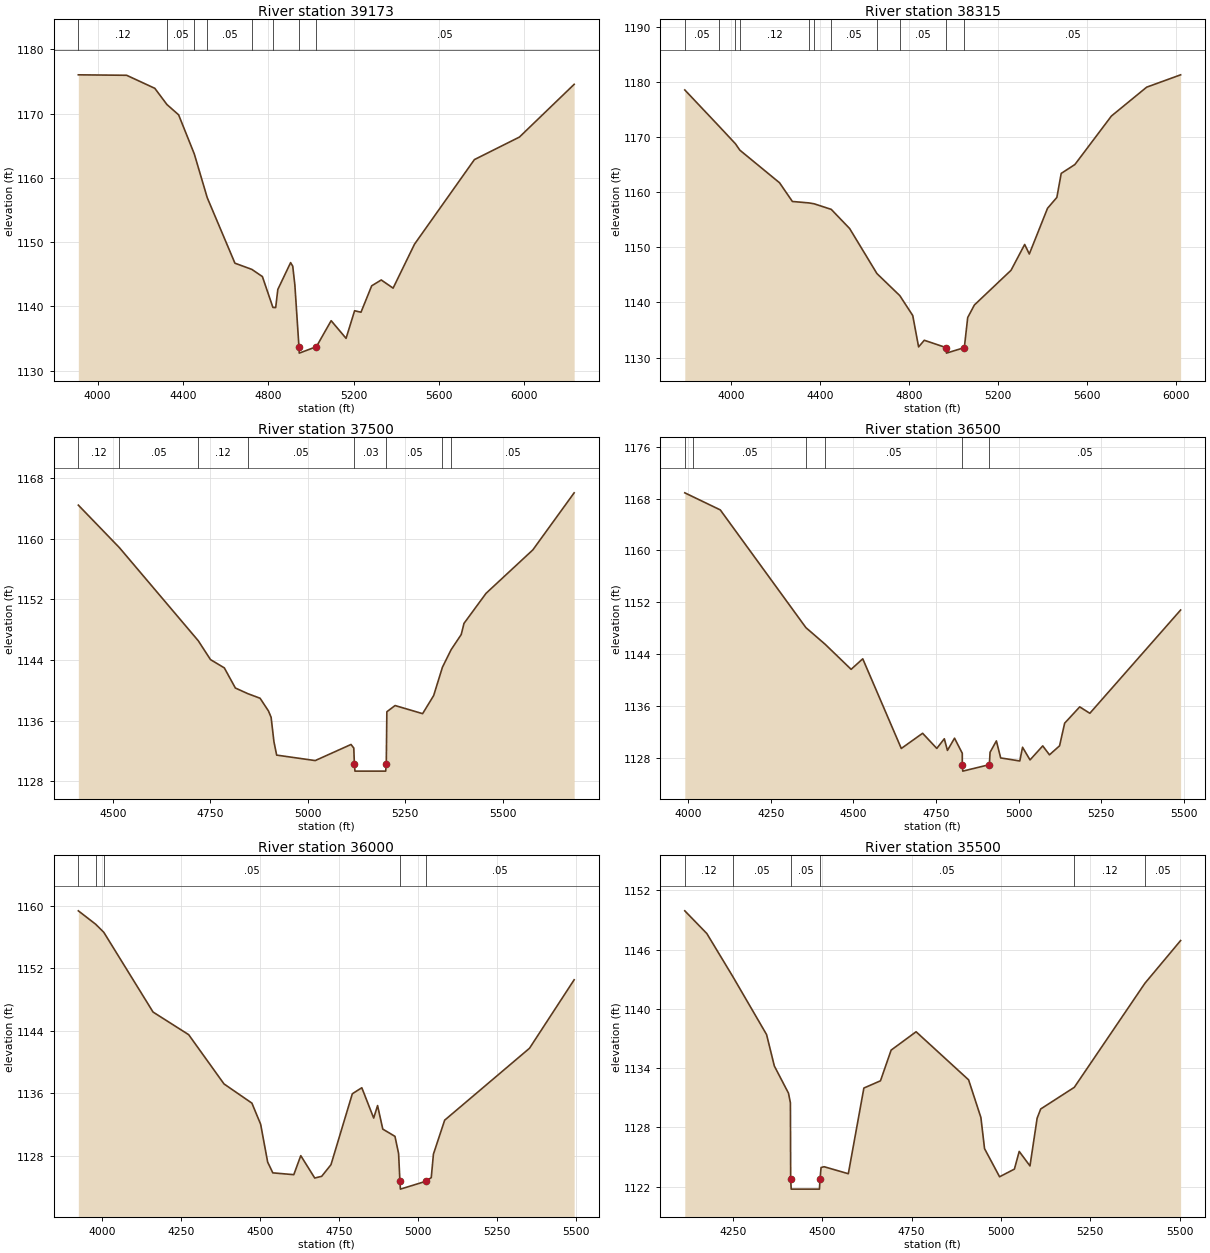
Type RM Length L Ch R = 1 ,39173   ,858,858,858
BEGIN DESCRIPTION:
Mapping XS 880c5148
END DESCRIPTION:
XS GIS Cut Line= 4
      2764378.73     10249684.81      2763597.46     10249545.92
      2763024.55     10249563.28      2762070.18     10249650.04
#Sta/Elev= 30
  3909.6 1176.04  4136.1 1175.97  4268.2 1173.94    4325 1171.42  4379.9 1169.81
  4453.3 1163.73  4514.2  1156.9    4644 1146.71  4723.1 1145.75  4772.7 1144.63
    4822 1139.83    4835  1139.8    4845 1142.62    4905  1146.8    4915 1146.25
    4925 1143.32  4944.1 1133.71  4945.6 1132.71  5025.9 1133.71  5095.1 1137.76
  5165.1 1135.01  5205.1 1139.31  5235.1 1139.08  5285.2 1143.19    5330  1144.1
  5385.6 1142.83    5486 1149.67  5766.8 1162.84    5978 1166.35  6234.6 1174.56
#Mann= 8 ,-1 , 0
  3909.6     .12       0    4325     .05       0  4453.3     .12       0
  4514.2     .05       0  4723.1     .12       0    4822     .05       0
  4944.1     .03       0  5025.9     .05       0
Bank Sta=4944.1,5025.9
XS Rating Curve= 0 ,0
Exp/Cntr=0.3,0.1

Type RM Length L Ch R = 1 ,38315   ,815,815,815
BEGIN DESCRIPTION:
Mapping XS 63355f08
END DESCRIPTION:
XS GIS Cut Line= 3
      2764526.31     10249103.22       2763493.3     10248755.99
      2762382.17     10248504.25
#Sta/Elev= 30
  3793.1 1178.52  3946.5 1171.97  4020.8 1168.76  4040.7  1167.6  4219.1 1161.69
  4276.8  1158.3  4351.4 1158.04  4374.6 1157.88  4451.5 1156.87  4534.3 1153.39
  4656.9 1145.23  4759.6 1141.24  4817.9 1137.63  4844.2 1131.94  4869.8 1133.14
  4967.9 1131.81  4969.4 1130.81  5049.8 1131.81    5065 1137.26  5095.1 1139.54
  5259.8 1145.83  5321.1 1150.51  5341.9 1148.78  5423.9 1157.07  5465.8 1159.04
  5485.4 1163.39  5546.9    1165    5711 1173.79  5869.4 1179.02  6022.2 1181.26
#Mann= 11 ,-1 , 0
  3793.1     .05       0  3946.5     .12       0  4020.8     .05       0
  4040.7     .12       0  4351.4     .05       0  4374.6     .12       0
  4451.5     .05       0  4656.9     .12       0  4759.6     .05       0
  4967.9     .03       0  5049.8     .05       0
Bank Sta=4967.9,5049.8
XS Rating Curve= 0 ,0
Exp/Cntr=0.3,0.1

Type RM Length L Ch R = 1 ,37500   ,1000,1000,1000
BEGIN DESCRIPTION:
SAN FERNANDO CREEK 75.0
END DESCRIPTION:
XS GIS Cut Line= 3
      2764205.65     10248503.08      2763793.55     10248081.97
      2763305.69     10247603.12
#Sta/Elev= 30
  4410.8  1164.4  4516.2  1158.8  4718.6 1146.54  4750.1 1144.05  4785.6 1142.96
  4813.9 1140.31  4846.1 1139.56  4877.4 1138.96  4898.7  1137.3  4905.7 1136.45
  4912.9 1133.25  4919.9 1131.47  5018.9 1130.75  5110.8 1132.87  5117.9  1132.4
  5119.4 1130.36  5120.9 1129.36  5199.8 1129.36  5201.3 1130.36  5202.8 1137.18
  5223.9    1138  5294.6 1136.93  5322.9 1139.31  5345.5 1143.05  5367.8 1145.36
  5393.7 1147.35  5400.8 1148.82  5457.4 1152.78  5577.5  1158.5  5683.6 1166.02
#Mann= 8 ,-1 , 0
  4410.8     .12       0  4516.2     .05       0  4718.6     .12       0
  4846.1     .05       0  5119.4     .03       0  5201.3     .05       0
  5345.5     .12       0  5367.8     .05       0
Bank Sta=5119.4,5201.3
XS Rating Curve= 0 ,0
Exp/Cntr=0.3,0.1

Type RM Length L Ch R = 1 ,36500   ,500,500,500
BEGIN DESCRIPTION:
SAN FERNANDO CREEK 73.0
END DESCRIPTION:
XS GIS Cut Line= 3
      2764555.67     10248153.09      2764187.12      10247212.3
       2763705.7     10247303.11
#Sta/Elev= 30
  3989.6 1168.91  4015.2 1168.28    4097 1166.27    4356 1148.08  4414.6 1145.49
  4492.9 1141.63  4528.1 1143.26  4644.7  1129.4  4709.2 1131.75  4752.1 1129.41
  4774.9  1130.9  4784.3  1129.1  4805.8 1130.99  4829.2 1128.66  4829.3  1126.9
  4830.8  1125.9  4911.2  1126.9  4913.3 1128.81  4932.4 1130.57  4945.4 1127.94
  5003.3 1127.47  5011.6 1129.59  5034.2 1127.63  5072.7  1129.8    5093 1128.42
  5123.6 1129.81    5139 1133.31  5184.6 1135.83  5215.2 1134.84  5489.9  1150.8
#Mann= 6 ,-1 , 0
  3989.6     .12       0  4015.2     .05       0    4356     .12       0
  4414.6     .05       0  4829.3     .03       0  4911.2     .05       0
Bank Sta=4829.3,4911.2
XS Rating Curve= 0 ,0
Exp/Cntr=0.3,0.1

Type RM Length L Ch R = 1 ,36000   ,500,500,500
BEGIN DESCRIPTION:
SAN FERNANDO CREEK 72.0
END DESCRIPTION:
XS GIS Cut Line= 3
      2764955.67     10247753.09      2764459.18     10246798.03
      2764105.68      10246453.1
#Sta/Elev= 30
  3923.6 1159.32  3978.7  1157.6  4004.3 1156.57  4160.3 1146.37    4273 1143.48
  4384.9 1137.18  4473.3 1134.72    4501 1132.02  4523.2 1127.18  4539.6  1125.8
    4606 1125.57  4628.1    1128  4672.3 1125.14  4694.4 1125.36  4723.8 1126.85
  4791.4 1135.92  4821.4 1136.69    4859 1132.81  4871.3 1134.41  4887.8  1131.4
  4926.4 1130.47  4937.9 1128.27  4942.1 1124.72  4943.6 1123.72    5024 1124.72
  5041.3 1125.19  5048.3 1128.21  5083.8 1132.54  5352.5 1141.74  5493.9  1150.5
#Mann= 5 ,-1 , 0
  3923.6     .05       0  3978.7     .12       0  4004.3     .05       0
  4942.1     .03       0    5024     .05       0
Bank Sta=4942.1,5024
XS Rating Curve= 0 ,0
Exp/Cntr=0.3,0.1

Type RM Length L Ch R = 1 ,35500   ,500,500,500
BEGIN DESCRIPTION:
SAN FERNANDO CREEK 71.0
END DESCRIPTION:
XS GIS Cut Line= 3
       2765155.7     10247253.14      2764806.66     10246441.08
       2764305.7     10246403.11
#Sta/Elev= 30
  4116.1 1149.93  4177.7 1147.63  4249.9  1143.3  4344.7  1137.4  4366.5 1134.21
    4406 1131.46  4411.4 1130.48  4412.1 1122.74  4413.6 1121.74  4492.6 1121.74
  4494.1 1122.74  4497.1 1123.93  4505.6 1124.01  4573.3  1123.3  4616.8 1131.98
  4663.2 1132.71    4693 1135.82  4762.8 1137.68  4909.6 1132.81    4944 1128.99
  4954.2 1125.84  4996.2 1122.99  5037.7 1123.77  5051.1 1125.56  5081.2 1124.09
  5101.3 1128.94  5111.3 1129.86  5205.1 1132.05  5402.5 1142.59  5502.4 1146.92
#Mann= 6 ,-1 , 0
  4116.1     .12       0  4249.9     .05       0  4412.1     .05       0
  4494.1     .05       0  5205.1     .12       0  5402.5     .05       0
Bank Sta=4412.1,4494.1
XS Rating Curve= 0 ,0
Exp/Cntr=0.3,0.1

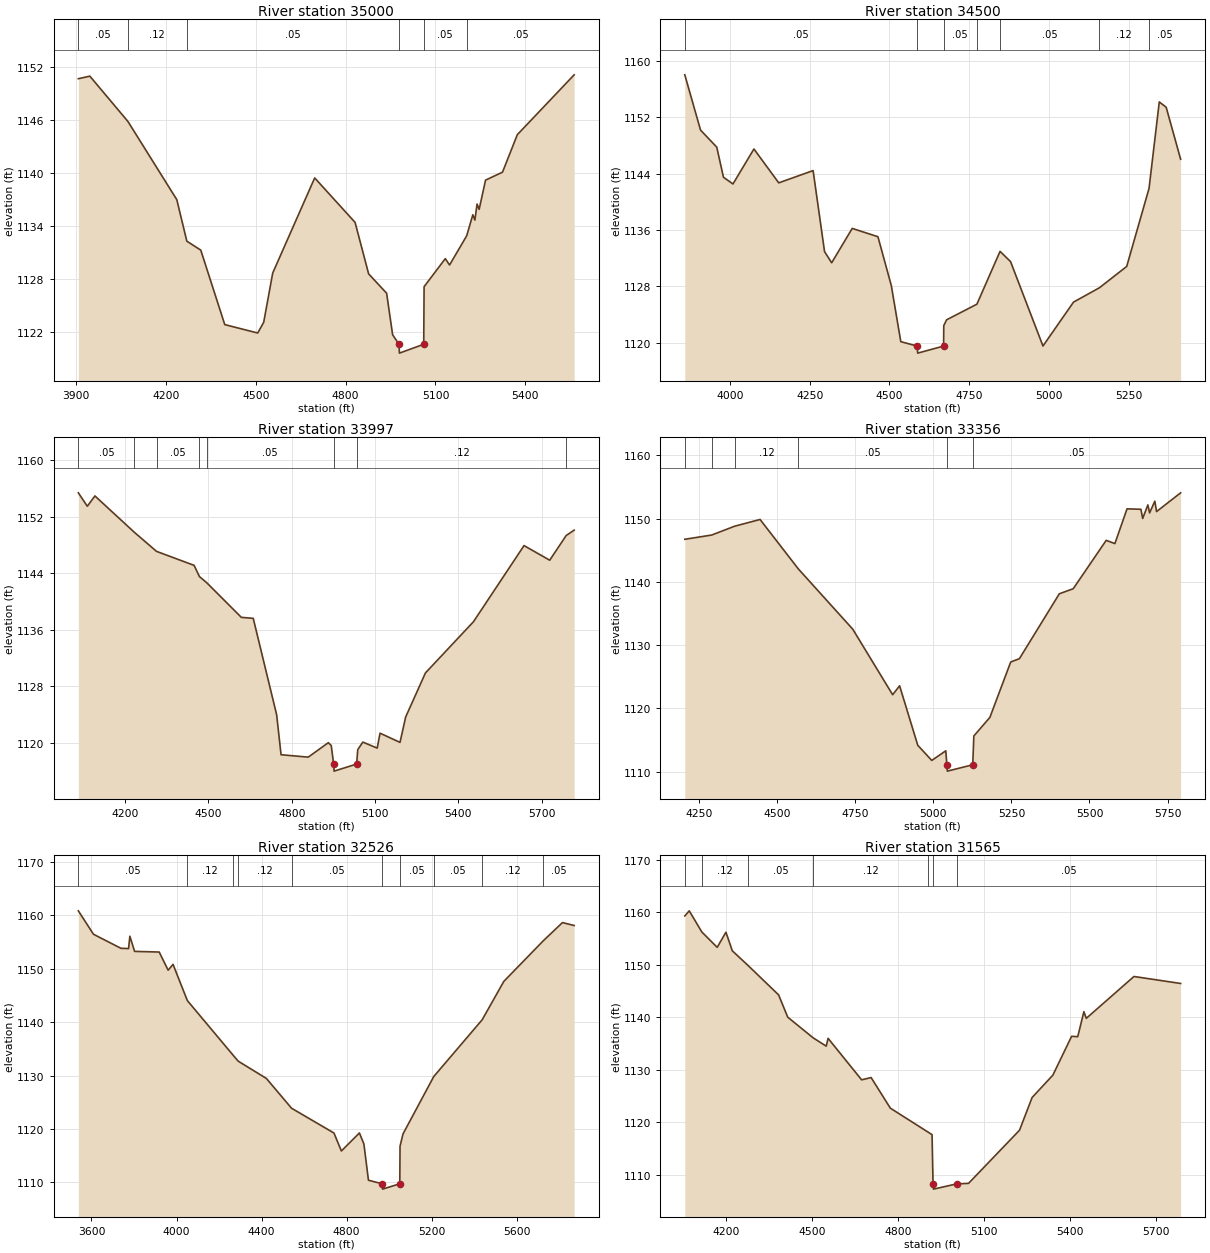
Type RM Length L Ch R = 1 ,35000   ,500,500,500
BEGIN DESCRIPTION:
SAN FERNANDO CREEK 70.0
END DESCRIPTION:
XS GIS Cut Line= 3
      2765255.45      10247271.6      2765226.17      10246180.1
      2764839.76     10245770.91
#Sta/Elev= 30
  3908.1 1150.63  3946.6 1150.92  4073.5 1145.81  4236.7 1136.98  4270.2 1132.29
  4316.7 1131.28  4396.8 1122.87  4506.8 1121.92  4526.8 1123.14  4556.8 1128.69
  4696.9 1139.43  4831.7 1134.41  4876.9  1128.6    4937 1126.41    4957 1121.72
  4978.2 1120.65  4979.7 1119.65  5060.8 1120.65    5062 1127.15  5132.8 1130.32
    5147  1129.6  5204.1 1132.89  5224.6 1135.27  5231.5 1134.67  5238.8 1136.48
  5245.7 1135.88  5267.1 1139.18  5323.7 1140.08  5373.1 1144.31  5562.8 1151.07
#Mann= 6 ,-1 , 0
  3908.1     .05       0  4073.5     .12       0  4270.2     .05       0
  4978.2     .03       0  5060.8     .05       0  5204.1     .05       0
Bank Sta=4978.2,5060.8
XS Rating Curve= 0 ,0
Exp/Cntr=0.3,0.1

Type RM Length L Ch R = 1 ,34500   ,503,503,503
BEGIN DESCRIPTION:
SAN FERNANDO CREEK 69.0
END DESCRIPTION:
XS GIS Cut Line= 3
      2766355.69     10247003.11      2765711.06     10246060.93
      2765505.67     10245703.08
#Sta/Elev= 30
  3858.4 1158.03  3907.8 1150.18  3958.6 1147.76  3979.6 1143.49  4009.4 1142.53
  4075.1  1147.5  4152.9 1142.69  4260.6 1144.43  4296.5 1132.92  4318.8 1131.34
  4383.2 1136.22  4463.8 1135.04  4505.7 1128.11  4535.5 1120.14  4586.9 1119.51
  4588.4 1118.51  4669.6 1119.51  4670.2 1122.42  4679.1 1123.24    4774 1125.46
  4846.6 1132.96  4879.5 1131.51  4981.1 1119.52  5076.8 1125.75    5158 1127.79
  5243.6 1130.82  5313.6  1141.9  5345.7 1154.18  5367.3 1153.43  5412.6 1146.05
#Mann= 7 ,-1 , 0
  3858.4     .05       0  4586.9     .03       0  4669.6     .05       0
    4774     .12       0  4846.6     .05       0    5158     .12       0
  5313.6     .05       0
Bank Sta=4586.9,4669.6
XS Rating Curve= 0 ,0
Exp/Cntr=0.3,0.1

Type RM Length L Ch R = 1 ,33997   ,641,641,641
BEGIN DESCRIPTION:
Mapping XS 8bec5576
END DESCRIPTION:
XS GIS Cut Line= 4
      2766609.62     10246941.76      2766262.39     10246351.47
      2766149.55     10245926.13      2766028.31     10245276.64
#Sta/Elev= 30
  4031.3 1155.41  4063.7 1153.51    4091 1154.97  4233.4 1149.81    4313 1147.12
  4448.3 1145.14  4467.3 1143.56  4494.4 1142.66  4618.3 1137.78  4661.2 1137.64
  4745.5 1123.99  4761.4 1118.33  4859.3 1117.99  4931.7 1120.04  4942.1 1119.63
  4950.8 1117.01  4952.3 1116.01  5033.5 1117.01  5037.6 1119.05  5055.9 1120.12
  5107.6 1119.27  5117.9 1121.38  5189.8 1120.08  5210.1 1123.67  5281.3 1129.91
  5454.3 1137.16  5636.4 1147.94  5728.9 1145.87  5788.1 1149.36  5816.9 1150.13
#Mann= 8 ,-1 , 0
  4031.3     .05       0  4233.4     .12       0    4313     .05       0
  4467.3     .12       0  4494.4     .05       0  4950.8     .03       0
  5033.5     .12       0  5788.1     .12       0
Bank Sta=4950.8,5033.5
XS Rating Curve= 0 ,0
Exp/Cntr=0.3,0.1

Type RM Length L Ch R = 1 ,33356   ,830,830,830
BEGIN DESCRIPTION:
Mapping XS 7c86bb72
END DESCRIPTION:
XS GIS Cut Line= 2
      2767104.41     10246637.93      2766383.93     10245223.01
#Sta/Elev= 30
  4204.1 1146.72  4290.2 1147.39    4364 1148.79  4445.2 1149.85  4567.5 1142.05
  4741.9 1132.52  4869.7 1122.16    4892 1123.57  4950.2 1114.17    4995 1111.78
  5039.9  1113.3  5043.4 1111.09  5044.9 1110.09  5126.2 1111.09  5129.7 1115.64
  5181.1 1118.58  5247.8 1127.33  5275.7 1127.86  5403.5 1138.11    5448 1138.91
  5553.6 1146.55  5581.4 1146.04  5620.3 1151.53  5664.8 1151.46  5670.4 1150.01
    5687 1152.15  5692.6 1150.89  5709.3 1152.74  5714.9  1151.1  5791.9 1154.06
#Mann= 6 ,-1 , 0
  4204.1     .12       0  4290.2     .05       0    4364     .12       0
  4567.5     .05       0  5043.4     .03       0  5126.2     .05       0
Bank Sta=5043.4,5126.2
XS Rating Curve= 0 ,0
Exp/Cntr=0.3,0.1

Type RM Length L Ch R = 1 ,32526   ,961,961,961
BEGIN DESCRIPTION:
Mapping XS 97a85e65
END DESCRIPTION:
XS GIS Cut Line= 3
      2768485.27     10246171.03      2767481.76     10245495.94
      2766670.26     10244720.91
#Sta/Elev= 30
  3538.3 1160.87  3609.6 1156.48  3738.6 1153.85  3774.6  1153.8  3780.6 1156.11
  3802.9 1153.27  3918.6 1153.15  3960.6 1149.75  3983.7 1150.84  4050.9 1144.06
  4267.5 1133.76  4289.9 1132.71  4422.5 1129.47  4540.9 1123.89  4740.4 1119.24
  4775.2 1115.88  4860.1 1119.26  4881.2 1117.18  4902.6  1110.4  4967.2 1109.73
  4968.7 1108.73    5050 1109.73  5051.1 1116.77  5065.2 1119.08  5209.6 1129.82
  5437.4 1140.46  5539.2 1147.65  5724.5 1155.25    5815 1158.67  5869.9 1158.12
#Mann= 10 ,-1 , 0
  3538.3     .05       0  4050.9     .12       0  4267.5     .05       0
  4289.9     .12       0  4540.9     .05       0  4967.2     .03       0
    5050     .05       0  5209.6     .05       0  5437.4     .12       0
  5724.5     .05       0
Bank Sta=4967.2,5050
XS Rating Curve= 0 ,0
Exp/Cntr=0.3,0.1

Type RM Length L Ch R = 1 ,31565   ,800,800,800
BEGIN DESCRIPTION:
Mapping XS 6f7d723f
END DESCRIPTION:
XS GIS Cut Line= 3
      2768886.71     10245204.02      2767910.54     10244711.37
      2767363.15     10244382.94
#Sta/Elev= 30
  4055.1 1159.33  4070.6 1160.31  4114.7 1156.27  4168.3 1153.35  4198.8 1156.23
  4221.1 1152.69  4277.2 1149.83  4382.8 1144.28  4414.7 1140.03    4504 1136.07
  4549.1 1134.51  4555.6    1136  4672.7 1128.09  4705.9 1128.52    4773 1122.69
  4904.2 1118.14  4918.7 1117.64  4922.2 1108.25  4923.7 1107.25    5005 1108.25
  5046.2 1108.35  5224.2 1118.48  5268.2 1124.72  5340.8 1128.99  5406.2 1136.39
  5427.6 1136.31    5449 1141.08  5457.4 1139.81  5623.9 1147.79  5786.9 1146.46
#Mann= 7 ,-1 , 0
  4055.1     .05       0  4114.7     .12       0  4277.2     .05       0
    4504     .12       0  4904.2     .05       0  4922.2     .05       0
    5005     .05       0
Bank Sta=4922.2,5005
XS Rating Curve= 0 ,0
Exp/Cntr=0.3,0.1

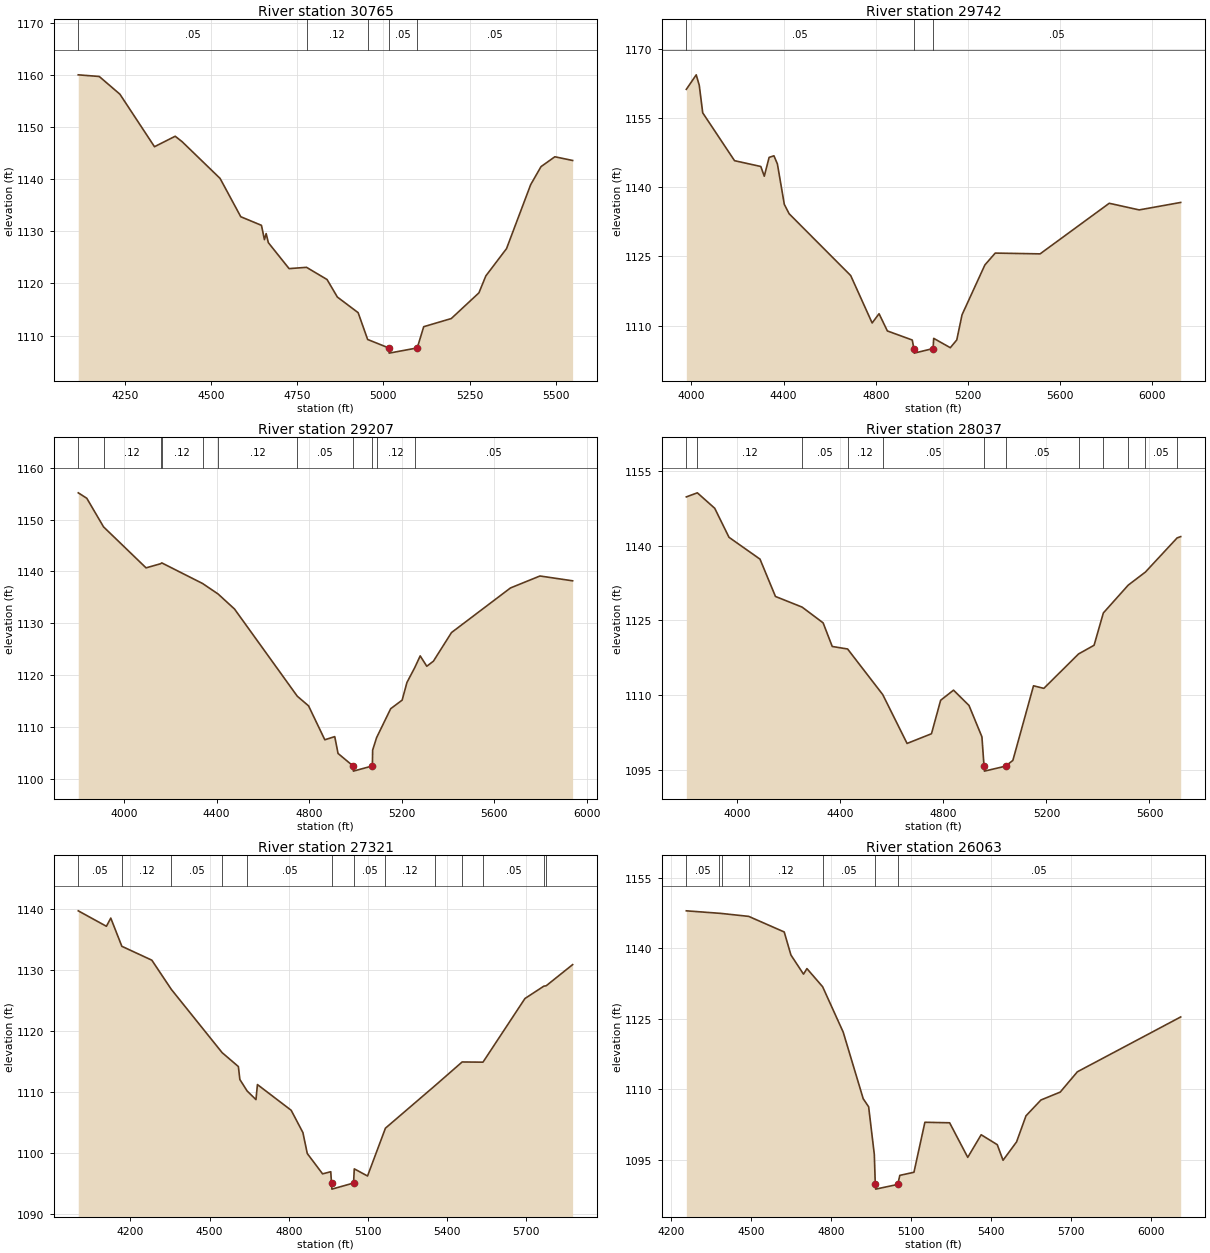
Type RM Length L Ch R = 1 ,30765   ,1023,1023,1023
BEGIN DESCRIPTION:
Mapping XS b22e72c8
END DESCRIPTION:
XS GIS Cut Line= 2
      2769096.55     10244045.41      2767664.17     10243999.79
#Sta/Elev= 30
  4115.5 1160.04  4176.4 1159.72  4236.4 1156.31  4336.5 1146.24  4396.5 1148.25
  4416.5 1147.21  4526.6 1140.16  4586.6  1132.8  4646.6 1131.15  4655.2  1128.4
  4660.2 1129.56  4666.6 1127.82  4726.7 1122.84  4777.2 1123.09  4836.7 1120.75
  4866.7 1117.38  4926.8 1114.39  4954.4 1109.24  5015.4 1107.62  5016.9 1106.62
  5098.2 1107.62  5116.9 1111.69  5196.9 1113.26    5277 1118.19    5297 1121.44
    5357 1126.68    5427 1138.96    5457 1142.42  5497.1 1144.31  5548.6  1143.6
#Mann= 5 ,-1 , 0
  4115.5     .05       0  4777.2     .12       0  4954.4     .05       0
  5015.4     .05       0  5098.2     .05       0
Bank Sta=5015.4,5098.2
XS Rating Curve= 0 ,0
Exp/Cntr=0.3,0.1

Type RM Length L Ch R = 1 ,29742   ,535,535,535
BEGIN DESCRIPTION:
Mapping XS eec86300
END DESCRIPTION:
XS GIS Cut Line= 3
      2768941.42     10243616.63      2767810.19     10242859.43
      2767025.63      10242886.8
#Sta/Elev= 30
  3977.7  1161.3  4020.7 1164.45  4033.9 1162.16  4048.9 1156.19    4187  1145.8
  4301.1 1144.54  4316.1 1142.43  4337.1 1146.52  4358.1 1146.86  4373.1 1145.09
  4403.1 1136.31  4424.1 1134.27  4691.3 1120.85  4784.4 1110.55  4814.4 1112.56
  4850.5 1108.82  4958.5 1106.85  4965.7    1105  4967.2    1104  5049.1    1105
  5051.6 1107.21  5123.7 1105.18  5151.8 1106.86  5174.7 1112.33  5273.8 1123.15
  5318.8 1125.73  5513.6 1125.56  5813.8 1136.55  5943.8 1135.11    6124 1136.73
#Mann= 3 ,-1 , 0
  3977.7     .05       0  4965.7     .03       0  5049.1     .05       0
Bank Sta=4965.7,5049.1
XS Rating Curve= 0 ,0
Exp/Cntr=0.3,0.1

Type RM Length L Ch R = 1 ,29207   ,1170,1170,1170
BEGIN DESCRIPTION:
Mapping XS 3af6b73a
END DESCRIPTION:
XS GIS Cut Line= 2
      2769123.85     10243507.12      2767746.31     10241874.14
#Sta/Elev= 30
  3802.4 1155.15  3839.3  1154.1  3911.7 1148.58  4095.4 1140.67  4157.9 1141.46
  4163.3 1141.63  4339.7 1137.65  4406.6 1135.63  4477.8 1132.72  4748.9  1115.9
  4797.6 1114.04  4867.9 1107.49  4910.8  1108.1  4925.1 1104.85  4989.9 1102.44
  4991.4 1101.44  5073.4 1102.44  5074.6  1105.5  5091.7 1107.91  5152.6 1113.49
    5202 1115.14  5222.9 1118.56  5256.5 1121.41  5280.1 1123.68  5308.6 1121.68
  5337.2 1122.66  5415.3 1128.18  5670.2 1136.79  5797.6  1139.1  5938.8 1138.17
#Mann= 11 ,-1 , 0
  3802.4     .05       0  3911.7     .12       0  4157.9     .05       0
  4163.3     .12       0  4339.7     .05       0  4406.6     .12       0
  4748.9     .05       0  4989.9     .05       0  5073.4     .05       0
  5091.7     .12       0  5256.5     .05       0
Bank Sta=4989.9,5073.4
XS Rating Curve= 0 ,0
Exp/Cntr=0.3,0.1

Type RM Length L Ch R = 1 ,28037   ,716,716,716
BEGIN DESCRIPTION:
Mapping XS 89d47658
END DESCRIPTION:
XS GIS Cut Line= 2
      2769315.46     10243388.57      2769406.69     10241472.74
#Sta/Elev= 30
  3803.1 1149.86  3845.9 1150.68  3913.3 1147.57  3968.7 1141.73  4088.9 1137.34
  4148.9 1129.83  4252.2 1127.69  4333.8 1124.52  4369.2 1119.77  4428.8 1119.26
  4565.1 1110.09  4659.5 1100.26  4754.2 1102.21  4789.7 1108.94  4839.7 1110.98
  4899.8  1107.9  4949.9 1101.59  4958.1 1095.69  4959.6 1094.69  5041.7 1095.69
    5070 1096.85  5150.1 1111.86  5190.1 1111.34  5324.7 1118.26    5385 1120.01
    5421 1126.51  5517.5 1132.11  5584.2 1134.74  5707.2 1141.61  5721.1 1141.87
#Mann= 12 ,-1 , 0
  3803.1     .05       0  3845.9     .12       0  4252.2     .05       0
  4428.8     .12       0  4565.1     .05       0  4958.1     .03       0
  5041.7     .05       0  5324.7     .12       0    5421     .05       0
  5517.5     .12       0  5584.2     .05       0  5707.2     .12       0
Bank Sta=4958.1,5041.7
XS Rating Curve= 0 ,0
Exp/Cntr=0.3,0.1

Type RM Length L Ch R = 1 ,27321   ,1258,1258,1258
BEGIN DESCRIPTION:
Mapping XS c40dd1c9
END DESCRIPTION:
XS GIS Cut Line= 3
      2769534.42     10243297.31      2769972.31     10242439.78
      2770382.75     10241628.01
#Sta/Elev= 30
  4002.7 1139.66  4109.3 1137.13  4125.9 1138.47  4167.8 1133.85  4281.4 1131.58
  4355.2  1126.8  4547.8 1116.43  4609.2 1114.16  4614.8 1112.04  4642.4 1110.16
  4675.8 1108.75  4681.4 1111.21  4809.2    1107  4853.6 1103.35  4870.2 1099.92
  4928.1 1096.59  4959.1 1096.94  4961.9 1095.09  4963.4 1094.09  5045.5 1095.09
  5048.2 1097.41  5098.4 1096.24  5166.2 1104.07    5355 1111.07  5456.7 1114.91
  5535.7 1114.88  5694.6  1125.3    5766 1127.32  5775.1 1127.39  5875.2 1130.85
#Mann= 13 ,-1 , 0
  4002.7     .05       0  4167.8     .12       0  4355.2     .05       0
  4547.8     .12       0  4642.4     .05       0  4961.9     .03       0
  5045.5     .05       0  5166.2     .12       0    5355     .05       0
  5456.7     .12       0  5535.7     .05       0    5766     .12       0
  5775.1     .05       0
Bank Sta=4961.9,5045.5
XS Rating Curve= 0 ,0
Exp/Cntr=0.3,0.1

Type RM Length L Ch R = 1 ,26063   ,443,443,443
BEGIN DESCRIPTION:
Mapping XS 5aeadbc2
END DESCRIPTION:
XS GIS Cut Line= 4
       2771130.9     10243361.22      2771249.51     10242987.15
      2770994.07     10242266.44      2770565.28     10241719.05
#Sta/Elev= 30
  4258.4 1147.93  4379.6 1147.42  4390.4 1147.37  4492.1 1146.75  4625.2 1143.44
  4650.3 1138.55  4697.5 1134.48  4710.3 1135.66  4769.1 1131.81  4846.1 1122.18
  4921.2 1108.02  4941.5 1106.31  4962.8 1096.19  4966.4 1089.82  4967.9 1088.82
  5050.7 1089.82  5058.3 1091.74  5111.3  1092.4  5152.3 1103.02    5245 1102.91
  5312.9 1095.57  5363.2 1100.37  5423.5 1098.26  5445.1 1094.95  5495.8 1098.85
  5531.1 1104.39  5587.1 1107.75  5659.4 1109.43  5723.6 1113.74  6110.8 1125.39
#Mann= 7 ,-1 , 0
  4258.4     .05       0  4379.6     .12       0  4390.4     .05       0
  4492.1     .12       0  4769.1     .05       0  4966.4     .03       0
  5050.7     .05       0
Bank Sta=4966.4,5050.7
XS Rating Curve= 0 ,0
Exp/Cntr=0.3,0.1

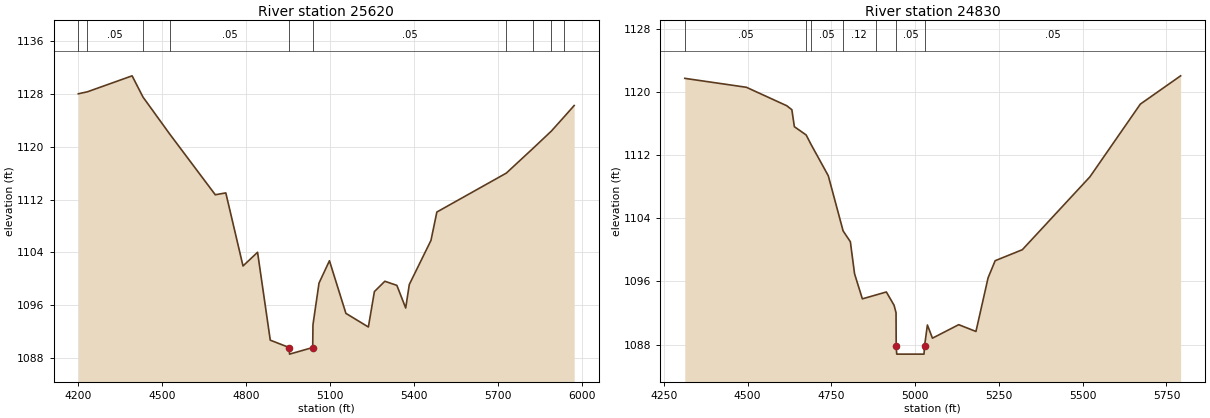
Type RM Length L Ch R = 1 ,25620   ,790,790,790
BEGIN DESCRIPTION:
Mapping XS 7f5bc832
END DESCRIPTION:
XS GIS Cut Line= 4
      2771550.56     10243087.48      2771486.71     10242467.15
      2771185.65     10241947.14      2771012.48     10241427.62
#Sta/Elev= 30
  4200.9 1127.98  4233.5 1128.28  4393.1 1130.69  4431.9 1127.49  4528.3 1121.85
  4690.4 1112.72    4728    1113  4789.5 1101.96  4841.5 1104.03  4886.9 1090.75
  4954.3 1089.64  4955.8 1088.64  5038.6 1089.64  5039.5 1093.08  5061.1 1099.37
  5098.4 1102.75  5157.2  1094.8  5237.5 1092.74  5259.1 1098.09  5296.4 1099.65
  5339.4 1099.03  5370.9 1095.61  5383.8 1099.16  5461.2 1105.82  5482.3 1110.11
  5730.5 1115.99  5826.3 1119.74  5891.7 1122.35  5938.4 1124.55    5973  1126.2
#Mann= 10 ,-1 , 0
  4200.9     .12       0  4233.5     .05       0  4431.9     .12       0
  4528.3     .05       0  4954.3     .03       0  5038.6     .05       0
  5730.5     .12       0  5826.3     .05       0  5891.7     .12       0
  5938.4     .05       0
Bank Sta=4954.3,5038.6
XS Rating Curve= 0 ,0
Exp/Cntr=0.3,0.1

Type RM Length L Ch R = 1 ,24830   ,353,353,353
BEGIN DESCRIPTION:
Mapping XS aa6d6b1b
END DESCRIPTION:
XS GIS Cut Line= 3
      2772599.69      10242211.7       2771605.3     10241563.98
      2771432.45     10241327.45
#Sta/Elev= 30
  4312.6 1121.72  4496.4 1120.59    4617 1118.25  4632.1 1117.75  4639.6  1115.6
  4674.8 1114.55  4689.3 1113.36  4740.8 1109.39  4785.1  1102.4  4806.7 1101.03
  4819.2 1096.98  4842.5  1093.8    4882 1094.28  4914.1 1094.67  4937.1 1092.99
    4943 1092.05  4943.5  1087.8    4945  1086.8  5026.5  1086.8    5028  1087.8
  5036.6 1090.49  5051.7 1088.82  5130.1 1090.53  5181.5 1089.67  5217.7 1096.46
  5238.8 1098.63  5319.9 1100.02  5521.6 1109.25  5672.1 1118.46  5792.3 1122.04
#Mann= 7 ,-1 , 0
  4312.6     .05       0  4674.8     .12       0  4689.3     .05       0
  4785.1     .12       0    4882     .05       0  4943.5     .05       0
    5028     .05       0
Bank Sta=4943.5,5028
XS Rating Curve= 0 ,0
Exp/Cntr=0.3,0.1