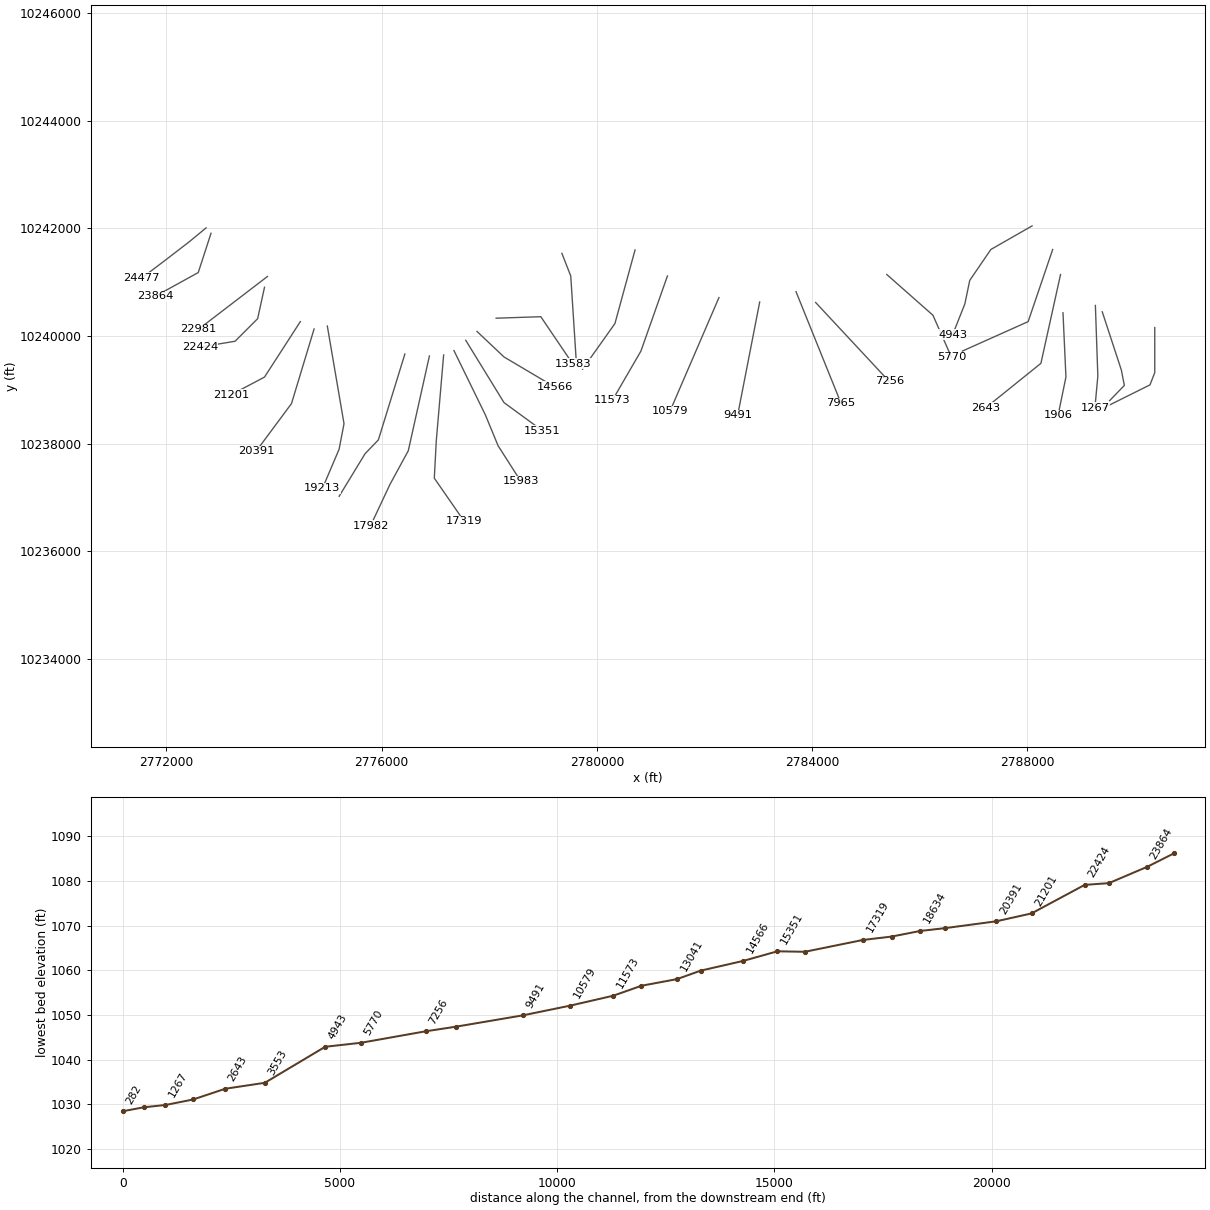
HEC-RAS study SAN FERNANDO CREEK.prj: SAN FERNANDO CREEK Base Level Engineering

--- SAN FERNANDO CREEK.g01 (geometry) --- (continued)

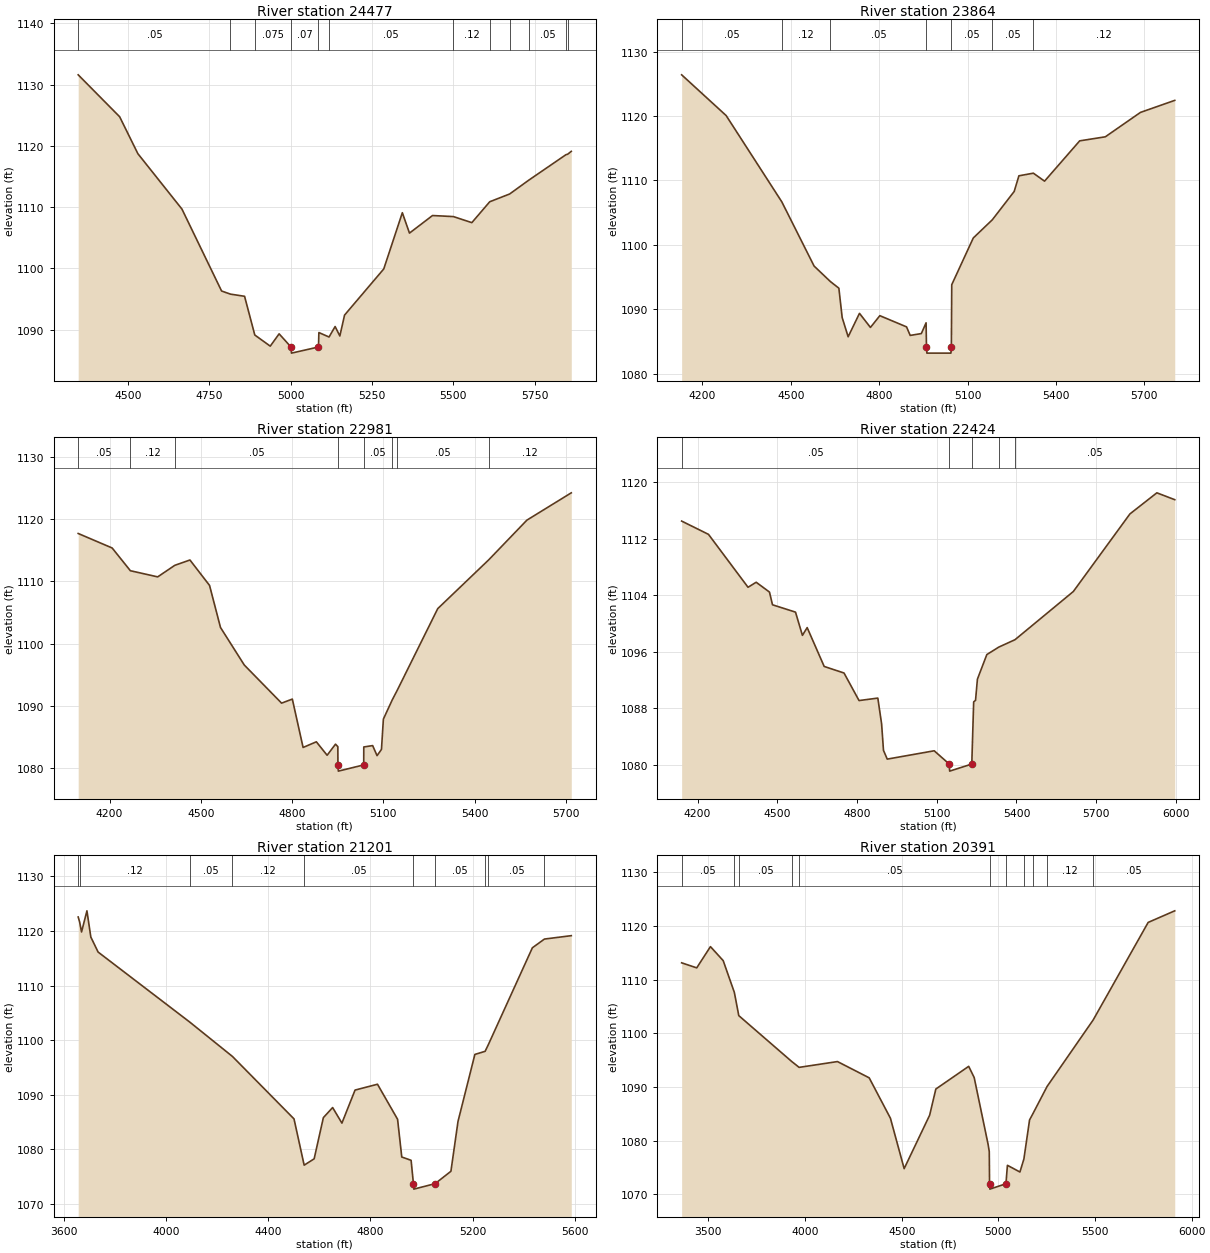
Type RM Length L Ch R = 1 ,24477   ,613,613,613
BEGIN DESCRIPTION:
Mapping XS f003bc97
END DESCRIPTION:
XS GIS Cut Line= 4
      2772736.53     10242010.99      2772426.36     10241755.56
      2771988.46     10241418.02      2771541.48      10241080.5
#Sta/Elev= 30
  4347.3  1131.6  4474.6 1124.76  4530.6 1118.73  4666.1 1109.68  4787.8 1096.31
  4815.1  1095.8  4858.4 1095.45  4889.8 1089.13  4937.3 1087.31  4964.6 1089.32
    5001 1087.17  5002.5 1086.17  5085.5 1087.17  5086.7 1089.53  5117.9  1088.8
  5136.6 1090.51  5151.1 1088.97  5165.6 1092.38    5286 1099.91  5343.1 1109.09
    5365 1105.76  5435.8 1108.63  5499.9 1108.46  5556.6 1107.47  5611.6 1110.88
  5672.8 1112.15  5731.4  1114.4  5845.7 1118.56  5851.3 1118.65  5862.1 1119.11
#Mann= 12 ,-1 , 0
  4347.3     .05       0  4815.1     .12       0  4889.8    .075       0
    5001     .07       0  5085.5    .075       0  5117.9     .05       0
  5499.9     .12       0  5611.6     .05       0  5672.8     .12       0
  5731.4     .05       0  5845.7     .12       0  5851.3     .05       0
Bank Sta=5001,5085.5
XS Rating Curve= 0 ,0
Exp/Cntr=0.3,0.1

Type RM Length L Ch R = 1 ,23864   ,883,883,883
BEGIN DESCRIPTION:
Mapping XS 1b4e76b7
END DESCRIPTION:
XS GIS Cut Line= 3
      2772827.77     10241910.66      2772590.57     10241180.82
      2771796.88     10240742.92
#Sta/Elev= 30
  4129.6 1126.41  4280.7 1120.08  4469.7 1106.67  4579.2  1096.7  4634.3  1094.3
  4663.3 1093.26  4674.6 1088.69  4694.8 1085.71  4733.3 1089.35  4770.5 1087.16
  4802.4 1088.99    4893 1087.25  4905.5 1085.92  4943.3 1086.21  4959.4 1087.88
  4960.7 1084.17  4962.2 1083.17  5043.7 1083.17  5045.2 1084.17  5046.5  1093.8
  5119.6 1101.06  5184.1 1103.88  5258.5 1108.29  5274.5 1110.72  5323.6 1111.13
  5361.6 1109.89  5480.8 1116.15  5567.9 1116.78  5687.1 1120.57  5803.5 1122.44
#Mann= 7 ,-1 , 0
  4129.6     .05       0  4469.7     .12       0  4634.3     .05       0
  4960.7     .07       0  5045.2     .05       0  5184.1     .05       0
  5323.6     .12       0
Bank Sta=4960.7,5045.2
XS Rating Curve= 0 ,0
Exp/Cntr=0.3,0.1

Type RM Length L Ch R = 1 ,22981   ,557,557,557
BEGIN DESCRIPTION:
Mapping XS 5a87b6b2
END DESCRIPTION:
XS GIS Cut Line= 2
      2773876.87     10241107.82      2772590.63     10240122.61
#Sta/Elev= 30
  4097.1 1117.68  4208.7 1115.35  4268.5  1111.7  4358.3 1110.71  4414.7 1112.57
  4464.3 1113.42  4528.7 1109.34  4564.7 1102.58  4642.9 1096.55  4765.4 1090.43
  4800.7 1091.08  4836.1 1083.31  4879.6 1084.22    4915 1082.06  4942.6 1083.84
  4950.3 1083.44  4950.5 1080.51    4952 1079.51  5035.3 1080.51  5035.5 1083.39
  5064.6 1083.61  5079.1    1082  5093.6    1083  5099.9 1087.87  5128.7 1090.92
  5146.2 1092.57  5278.5 1105.61  5446.1 1113.45  5571.4 1119.82  5717.3 1124.21
#Mann= 8 ,-1 , 0
  4097.1     .05       0  4268.5     .12       0  4414.7     .05       0
  4950.5     .05       0  5035.3     .05       0  5128.7     .12       0
  5146.2     .05       0  5446.1     .12       0
Bank Sta=4950.5,5035.3
XS Rating Curve= 0 ,0
Exp/Cntr=0.3,0.1

Type RM Length L Ch R = 1 ,22424   ,1223,1223,1223
BEGIN DESCRIPTION:
Mapping XS 6dffab70
END DESCRIPTION:
XS GIS Cut Line= 4
      2773822.17     10240907.15      2773694.44     10240323.27
      2773274.79     10239903.62       2772619.3     10239794.37
#Sta/Elev= 30
  4139.9 1114.52  4240.9 1112.64  4389.7 1105.15  4420.4 1105.86  4470.4 1104.47
  4481.8 1102.67  4568.4 1101.63  4594.4 1098.34  4612.3 1099.44  4676.3 1093.94
    4751 1093.01  4807.5 1089.11  4878.2 1089.46  4892.4 1085.82  4899.5 1082.06
  4913.6 1080.82  5090.4    1082    5147 1080.12  5148.5 1079.12  5231.8 1080.12
  5238.9 1088.92  5245.9 1089.14    5253 1092.14  5288.4 1095.62  5333.5 1096.68
  5394.6 1097.73    5614 1104.55  5826.9 1115.53  5928.3 1118.52  5995.6 1117.55
#Mann= 5 ,-1 , 0
  4139.9     .05       0    5147     .05       0  5231.8     .05       0
  5333.5     .12       0  5394.6     .05       0
Bank Sta=5147,5231.8
XS Rating Curve= 0 ,0
Exp/Cntr=0.3,0.1

Type RM Length L Ch R = 1 ,21201   ,810,810,810
BEGIN DESCRIPTION:
Mapping XS 5f8b94cb
END DESCRIPTION:
XS GIS Cut Line= 3
      2774488.14     10240268.54      2773822.16     10239237.65
      2773201.83     10238909.24
#Sta/Elev= 30
    3657 1122.57  3662.8 1121.63  3670.1 1119.83  3691.2  1123.7  3706.4  1118.9
  3734.9 1116.15  4093.3 1103.33  4260.5 1097.03  4501.4 1085.59  4541.1 1077.12
  4580.2 1078.28  4616.2 1085.82  4652.5 1087.67  4688.8 1084.82  4740.2 1090.87
    4828 1091.94  4906.6 1085.52    4923 1078.61  4959.5 1078.01  4968.6 1073.73
  4970.1 1072.73  5053.4 1073.73  5115.3    1076    5143 1085.13    5209  1097.4
  5249.1 1097.97  5262.1 1099.23    5434 1116.93  5481.2 1118.53  5586.2 1119.15
#Mann= 10 ,-1 , 0
    3657     .05       0  3662.8     .12       0  4093.3     .05       0
  4260.5     .12       0  4541.1     .05       0  4968.6     .03       0
  5053.4     .05       0  5249.1     .12       0  5262.1     .05       0
  5481.2     .12       0
Bank Sta=4968.6,5053.4
XS Rating Curve= 0 ,0
Exp/Cntr=0.3,0.1

Type RM Length L Ch R = 1 ,20391   ,1178,1178,1178
BEGIN DESCRIPTION:
Mapping XS dca53a2d
END DESCRIPTION:
XS GIS Cut Line= 3
      2774743.58      10240131.7      2774323.92     10238745.01
      2773667.04     10237860.05
#Sta/Elev= 30
  3361.6 1113.13  3439.6 1112.19  3510.6 1116.15  3576.5 1113.54  3634.3 1107.61
  3657.2 1103.29  3932.5  1094.7  3969.3 1093.65  4167.7 1094.73  4331.8  1091.7
  4441.6 1084.18  4512.7 1074.78  4644.5 1084.73  4676.6 1089.61  4846.6 1093.84
    4875 1091.75  4946.8 1079.33    4953 1077.96  4954.5 1071.96    4956 1070.96
  5039.3 1071.96  5046.9  1075.4  5111.6 1074.15  5132.1 1076.57  5161.5 1083.86
  5178.7 1085.01  5252.1 1090.09  5490.5 1102.48    5775 1120.66  5912.5 1122.82
#Mann= 11 ,-1 , 0
  3361.6     .05       0  3634.3     .12       0  3657.2     .05       0
  3932.5     .12       0  3969.3     .05       0  4954.5     .03       0
  5039.3     .05       0  5132.1     .12       0  5178.7     .05       0
  5252.1     .12       0  5490.5     .05       0
Bank Sta=4954.5,5039.3
XS Rating Curve= 0 ,0
Exp/Cntr=0.3,0.1

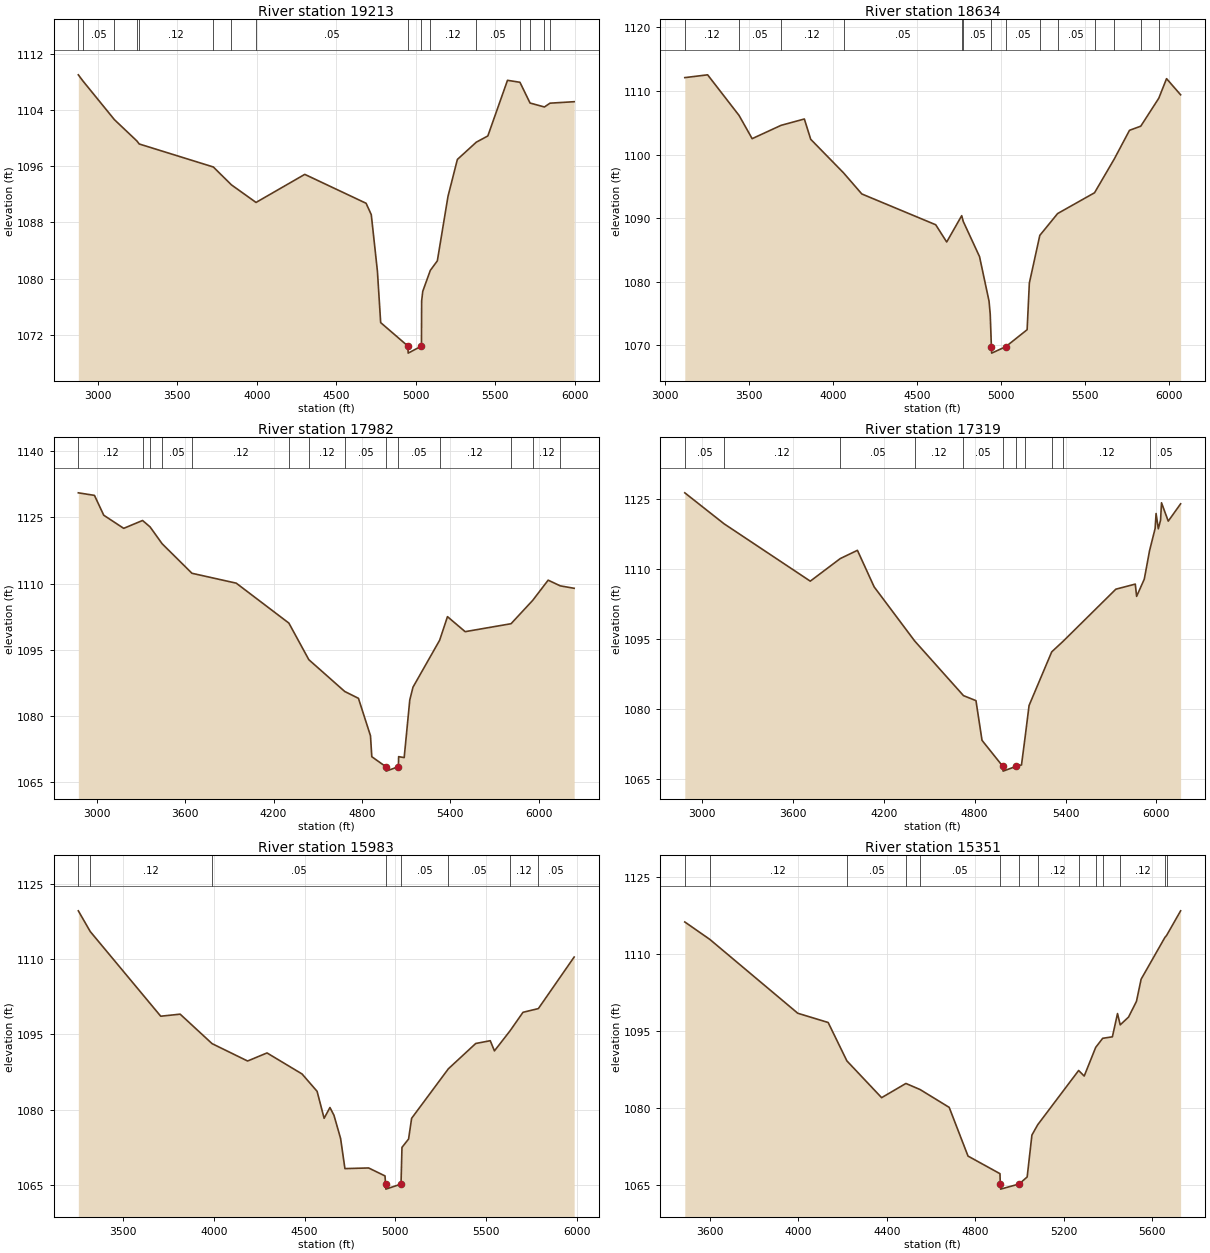
Type RM Length L Ch R = 1 ,19213   ,579,579,579
BEGIN DESCRIPTION:
Mapping XS 7d17b503
END DESCRIPTION:
XS GIS Cut Line= 4
       2774989.9      10240186.4      2775300.07     10238370.97
      2775208.84     10237896.59      2774898.94     10237167.42
#Sta/Elev= 30
  2878.3 1108.99  2907.1 1108.12    3105 1102.62  3246.4 1099.59  3261.1 1099.16
    3727 1095.89  3840.8 1093.35  3995.5 1090.85  4301.9 1094.84  4687.4 1090.73
    4720 1089.11  4758.6 1081.07    4779 1073.77  4950.4 1070.43  4951.9 1069.43
  5035.3 1070.43  5036.6 1076.85  5043.7 1078.22  5091.1 1081.19  5135.3 1082.55
  5202.3 1091.72  5261.2 1096.96  5380.4 1099.42  5452.7  1100.3  5576.3 1108.21
  5654.6 1107.93  5718.1 1104.98  5808.4 1104.42  5843.6 1104.96  5995.4 1105.17
#Mann= 16 ,-1 , 0
  2878.3     .12       0  2907.1     .05       0    3105     .12       0
  3246.4     .05       0  3261.1     .12       0    3727     .05       0
  3840.8     .12       0  3995.5     .05       0  4950.4     .03       0
  5035.3     .05       0  5091.1     .12       0  5380.4     .05       0
  5654.6     .12       0  5718.1     .05       0  5808.4     .12       0
  5843.6     .05       0
Bank Sta=4950.4,5035.3
XS Rating Curve= 0 ,0
Exp/Cntr=0.3,0.1

Type RM Length L Ch R = 1 ,18634   ,652,652,652
BEGIN DESCRIPTION:
Mapping XS 65ded84a
END DESCRIPTION:
XS GIS Cut Line= 4
      2776431.31     10239666.44      2775938.67     10238069.92
      2775692.35     10237814.48      2775209.74     10237022.27
#Sta/Elev= 30
  3117.3 1112.08  3253.3 1112.52  3440.5 1106.14  3518.5 1102.49  3690.5 1104.58
  3829.4 1105.58  3867.3 1102.39  4062.7 1097.12  4171.7  1093.8  4611.9 1088.96
  4677.2 1086.25  4766.7 1090.39  4776.1 1089.47  4872.8 1083.96  4929.4 1076.97
  4936.5 1074.92  4943.5 1069.79    4945 1068.79  5028.5 1069.79  5156.3 1072.47
  5169.6  1079.8  5231.9 1087.29  5337.9 1090.72  5557.9 1093.99  5676.3 1099.34
  5766.1  1103.8  5833.2 1104.45  5940.7 1108.85  5986.8 1111.92  6070.6 1109.38
#Mann= 14 ,-1 , 0
  3117.3     .12       0  3440.5     .05       0  3690.5     .12       0
  4062.7     .05       0  4766.7     .12       0  4776.1     .05       0
  4943.5     .05       0  5028.5     .05       0  5231.9     .12       0
  5337.9     .05       0  5557.9     .12       0  5676.3     .05       0
  5833.2     .12       0  5940.7     .05       0
Bank Sta=4943.5,5028.5
XS Rating Curve= 0 ,0
Exp/Cntr=0.3,0.1

Type RM Length L Ch R = 1 ,17982   ,663,663,663
BEGIN DESCRIPTION:
Mapping XS 4bad9050
END DESCRIPTION:
XS GIS Cut Line= 4
      2776887.45     10239629.95      2776495.17     10237869.22
      2776157.62     10237248.86      2775792.69     10236473.38
#Sta/Elev= 30
  2874.3 1130.54  2983.8 1129.96  3046.9 1125.47  3182.4  1122.5  3310.6 1124.28
  3361.6 1122.82  3443.2 1119.02  3645.9 1112.33  3946.8 1110.09  4304.2 1101.05
  4439.6 1092.77  4683.5 1085.57  4776.6 1084.02  4858.3 1075.55  4867.3  1070.8
    4963 1068.54  4964.5 1067.54    5048 1068.54  5049.5 1070.82  5087.2  1070.6
  5125.2 1083.64  5147.1 1086.55    5328 1097.17  5381.2 1102.51  5501.3 1099.11
  5812.9 1100.91  5960.1  1106.2    6065 1110.77  6147.1 1109.48  6241.5 1108.93
#Mann= 14 ,-1 , 0
  2874.3     .12       0  3310.6     .05       0  3361.6     .12       0
  3443.2     .05       0  3645.9     .12       0  4304.2     .05       0
  4439.6     .12       0  4683.5     .05       0    4963     .03       0
    5048     .05       0    5328     .12       0  5812.9     .05       0
  5960.1     .12       0  6147.1     .05       0
Bank Sta=4963,5048
XS Rating Curve= 0 ,0
Exp/Cntr=0.3,0.1

Type RM Length L Ch R = 1 ,17319   ,1336,1336,1336
BEGIN DESCRIPTION:
Mapping XS 81ba350d
END DESCRIPTION:
XS GIS Cut Line= 4
      2777152.01     10239648.18      2777015.17     10238051.67
      2776978.68     10237358.34      2777534.27     10236556.83
#Sta/Elev= 30
  2887.3 1126.36  3146.5 1119.73  3715.4 1107.45  3913.4 1112.29  4026.5 1114.05
  4136.9 1106.22  4404.6 1094.63  4726.4 1082.94  4808.7 1081.87  4848.7 1073.37
  4986.4 1067.78  4987.9 1066.78  5071.5 1067.78  5109.1  1068.1  5132.6 1073.95
  5159.1 1080.83  5308.5 1092.31  5384.8 1094.61  5731.7 1105.73  5860.1 1106.82
  5868.8 1104.19  5919.5 1107.89  5954.1 1113.96  5991.1 1118.75  5997.2 1121.93
  6012.1 1118.66  6026.9 1120.52    6033 1124.23  6077.6  1120.3  6159.2 1124.01
#Mann= 11 ,-1 , 0
  2887.3     .05       0  3146.5     .12       0  3913.4     .05       0
  4404.6     .12       0  4726.4     .05       0  4986.4     .03       0
  5071.5     .05       0  5132.6     .12       0  5308.5     .05       0
  5384.8     .12       0  5954.1     .05       0
Bank Sta=4986.4,5071.5
XS Rating Curve= 0 ,0
Exp/Cntr=0.3,0.1

Type RM Length L Ch R = 1 ,15983   ,632,632,632
BEGIN DESCRIPTION:
Mapping XS f46ddcab
END DESCRIPTION:
XS GIS Cut Line= 4
      2777343.58      10239730.3      2777927.46     10238535.19
      2778164.65     10237960.45      2778584.28     10237303.63
#Sta/Elev= 30
    3254 1119.61  3319.9 1115.47  3707.9  1098.6  3814.9 1099.01  3990.9 1093.13
  4186.4 1089.67  4293.4 1091.28  4486.3 1087.09  4569.2 1083.63    4608 1078.25
    4640  1080.4  4662.1 1078.86  4698.7 1074.23  4722.6 1068.22  4853.1 1068.35
  4943.4 1066.76  4946.4 1065.13  4947.9 1064.13  5031.5 1065.13  5036.8 1072.45
  5073.2 1074.12    5090 1078.25  5292.2 1088.11    5443 1093.16  5523.1 1093.72
  5546.2 1091.69  5632.2 1095.69  5703.5 1099.38  5788.1 1100.12  5985.3  1110.4
#Mann= 8 ,-1 , 0
    3254     .05       0  3319.9     .12       0  3990.9     .05       0
  4946.4     .03       0  5031.5     .05       0  5292.2     .05       0
  5632.2     .12       0  5788.1     .05       0
Bank Sta=4946.4,5031.5
XS Rating Curve= 0 ,0
Exp/Cntr=0.3,0.1

Type RM Length L Ch R = 1 ,15351   ,785,785,785
BEGIN DESCRIPTION:
Mapping XS 1e7e0bd4
END DESCRIPTION:
XS GIS Cut Line= 3
      2777562.53     10239921.88      2778274.13     10238763.26
      2778985.68     10238243.27
#Sta/Elev= 30
  3487.2  1116.3  3600.1 1112.91  3997.9 1098.51  4135.2 1096.71  4219.8 1089.23
  4376.8 1082.06  4486.5 1084.83  4550.9 1083.64  4682.2 1080.17  4767.3 1070.68
  4911.7 1067.25  4913.2 1065.24  4914.7 1064.24  4998.3 1065.24  5034.6 1066.61
  5056.1 1074.78  5082.4 1076.79  5267.3 1087.36  5292.4 1086.27  5344.5 1091.87
    5376 1093.63  5419.8 1093.92    5443 1098.45  5455.2 1096.25  5492.9 1097.77
  5528.7 1100.84  5549.6 1105.14  5657.2 1113.29  5664.6 1113.66  5728.2 1118.47
#Mann= 14 ,-1 , 0
  3487.2     .05       0  3600.1     .12       0  4219.8     .05       0
  4486.5     .12       0  4550.9     .05       0  4913.2     .03       0
  4998.3     .05       0  5082.4     .12       0  5267.3     .05       0
  5344.5     .12       0    5376     .05       0  5455.2     .12       0
  5657.2     .05       0  5664.6     .12       0
Bank Sta=4913.2,4998.3
XS Rating Curve= 0 ,0
Exp/Cntr=0.3,0.1

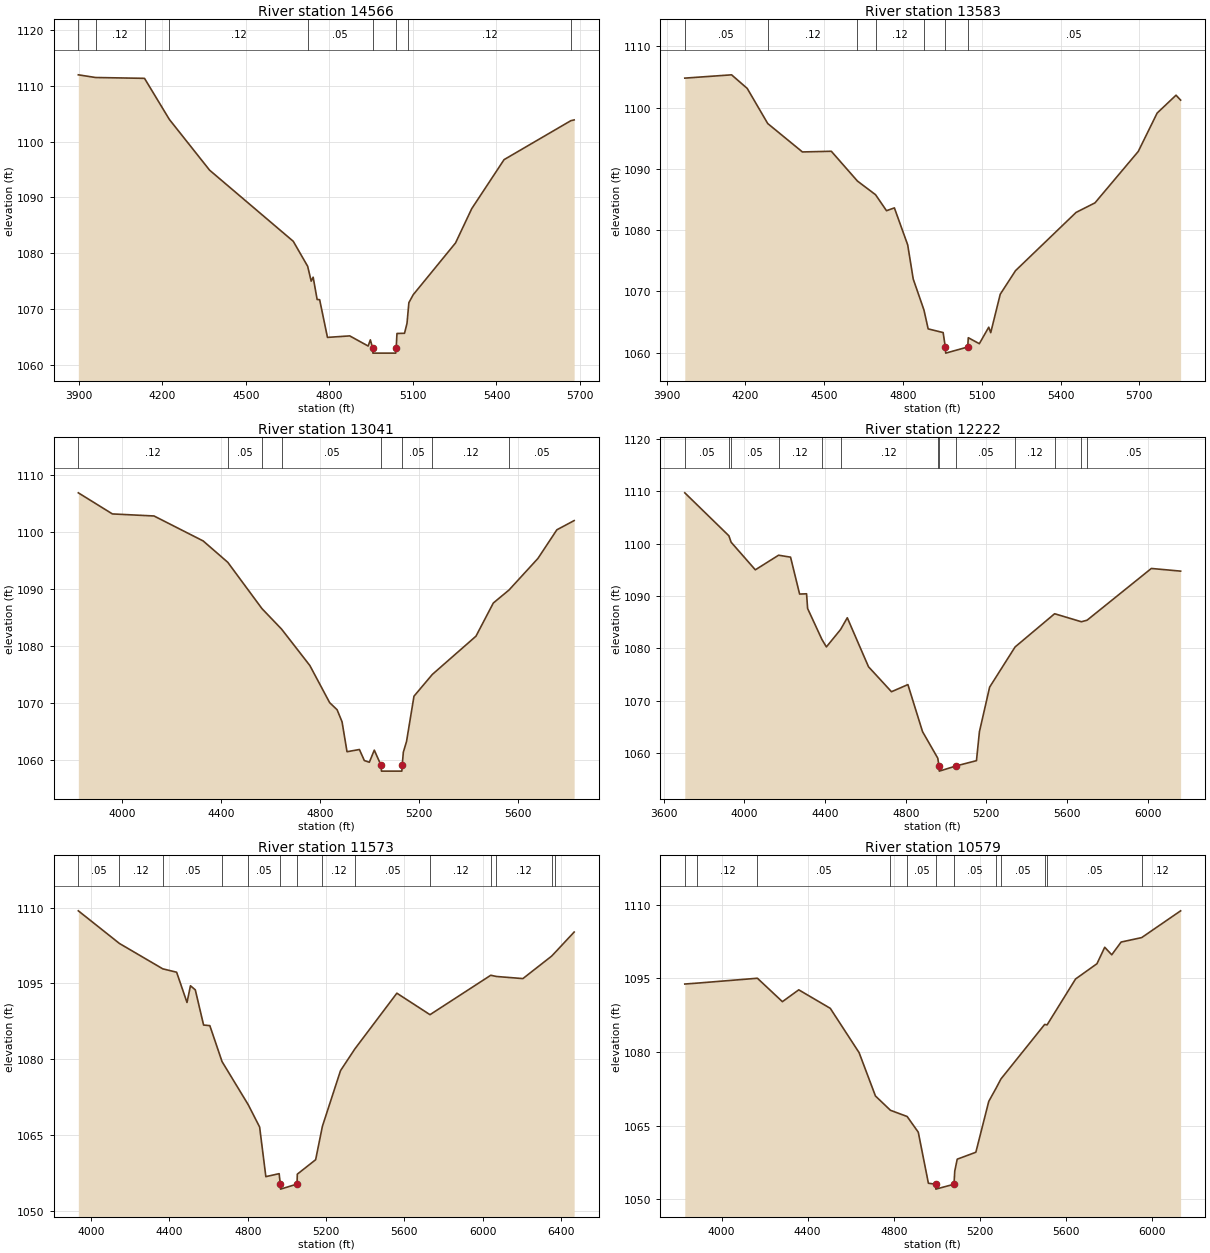
Type RM Length L Ch R = 1 ,14566   ,983,983,983
BEGIN DESCRIPTION:
Mapping XS 4b27b548
END DESCRIPTION:
XS GIS Cut Line= 3
      2777772.35     10240086.09      2778274.13     10239611.69
      2779212.22     10239056.12
#Sta/Elev= 30
  3898.2 1111.97  3960.2 1111.49  4135.9 1111.34  4225.1 1103.98  4369.7 1094.88
  4670.2 1082.13  4721.9 1077.65  4734.5 1074.99  4741.6  1075.7  4755.9  1071.7
  4764.9 1071.67    4793 1064.91  4872.9 1065.18  4939.2 1063.36    4947 1064.47
  4954.8 1063.09  4956.3 1062.09  5038.4 1062.09  5039.9 1063.09  5042.6 1065.61
  5069.8 1065.65  5078.7 1067.44  5082.8  1069.7  5085.4 1071.14    5101 1072.56
    5253 1081.84  5311.1 1087.98  5427.3 1096.77  5667.1 1103.75    5679 1103.89
#Mann= 9 ,-1 , 0
  3898.2     .05       0  3960.2     .12       0  4135.9     .05       0
  4225.1     .12       0  4721.9     .05       0  4954.8     .03       0
  5039.9     .05       0  5082.8     .12       0  5667.1     .05       0
Bank Sta=4954.8,5039.9
XS Rating Curve= 0 ,0
Exp/Cntr=0.3,0.1

Type RM Length L Ch R = 1 ,13583   ,542,542,542
BEGIN DESCRIPTION:
Mapping XS 8b1446eb
END DESCRIPTION:
XS GIS Cut Line= 3
      2778128.13     10240332.39      2778958.34     10240359.76
      2779551.03      10239484.4
#Sta/Elev= 30
  3969.5 1104.83  4147.6 1105.37  4207.2 1103.15  4285.3 1097.41  4417.3 1092.77
  4527.4 1092.88  4626.7 1088.02  4695.8 1085.78  4737.5 1083.17  4767.5 1083.63
  4818.2 1077.58  4839.2 1072.01  4880.1 1066.94  4896.1 1063.86  4953.1 1063.26
  4961.4  1060.9  4962.9  1059.9  5046.6  1060.9  5048.9 1062.42  5090.9 1061.44
  5126.8 1064.14  5134.3 1063.24  5170.5 1069.52  5228.6 1073.37  5459.3 1082.89
  5531.2 1084.45    5696 1092.85  5767.9 1099.12  5839.8 1102.04  5857.3 1101.24
#Mann= 7 ,-1 , 0
  3969.5     .05       0  4285.3     .12       0  4626.7     .05       0
  4695.8     .12       0  4880.1     .05       0  4961.4     .03       0
  5046.6     .05       0
Bank Sta=4961.4,5046.6
XS Rating Curve= 0 ,0
Exp/Cntr=0.3,0.1

Type RM Length L Ch R = 1 ,13041   ,819,819,819
BEGIN DESCRIPTION:
Mapping XS 0569ad3f
END DESCRIPTION:
XS GIS Cut Line= 3
      2779350.63      10241536.6      2779514.84     10241116.96
      2779615.12     10239567.12
#Sta/Elev= 30
  3821.9 1106.93  3959.6 1103.22  4127.8 1102.86  4326.5 1098.47    4426 1094.71
  4563.9 1086.58  4643.3 1082.97  4757.4 1076.58  4837.5 1070.05  4867.6  1068.8
  4887.7 1066.67  4907.7 1061.42  4957.8 1061.81  4977.7 1059.87  4997.9 1059.57
  5017.9  1061.7  5045.4 1059.01  5046.9 1058.01  5129.2 1058.01  5130.7 1059.01
  5135.3 1061.34  5148.2 1063.22  5178.3 1071.18  5252.3    1075  5428.8 1081.73
  5498.9 1087.56  5562.4 1089.85  5679.3  1095.4  5755.7 1100.43  5825.6 1102.05
#Mann= 8 ,-1 , 0
  3821.9     .12       0    4426     .05       0  4563.9     .12       0
  4643.3     .05       0  5045.4     .05       0  5130.7     .05       0
  5252.3     .12       0  5562.4     .05       0
Bank Sta=5045.4,5130.7
XS Rating Curve= 0 ,0
Exp/Cntr=0.3,0.1

Type RM Length L Ch R = 1 ,12222   ,649,649,649
BEGIN DESCRIPTION:
Mapping XS 9c214d73
END DESCRIPTION:
XS GIS Cut Line= 3
      2780709.94      10241600.5       2780335.9     10240232.04
       2779733.8     10239383.64
#Sta/Elev= 30
  3704.4 1109.69  3923.1 1101.48  3934.2 1100.25  4054.2 1094.98  4169.5 1097.77
  4228.9  1097.4  4273.8 1090.35  4308.3  1090.4  4313.5 1087.59  4384.5 1081.68
  4406.6 1080.25  4476.9 1083.57  4510.3 1085.82  4615.5 1076.46  4729.4 1071.69
  4810.9 1073.05  4883.5 1064.06  4959.1 1058.99  4965.1 1057.52  4966.6 1056.52
  5050.8 1057.52  5150.9 1058.52  5165.6 1064.05  5216.1 1072.56  5342.4 1080.24
  5538.5 1086.59    5671 1085.06  5699.3 1085.35  6018.2 1095.24  6163.4 1094.73
#Mann= 13 ,-1 , 0
  3704.4     .05       0  3923.1     .12       0  3934.2     .05       0
  4169.5     .12       0  4384.5     .05       0  4476.9     .12       0
  4959.1     .05       0  4965.1     .03       0  5050.8     .05       0
  5342.4     .12       0  5538.5     .05       0    5671     .12       0
  5699.3     .05       0
Bank Sta=4965.1,5050.8
XS Rating Curve= 0 ,0
Exp/Cntr=0.3,0.1

Type RM Length L Ch R = 1 ,11573   ,994,994,994
BEGIN DESCRIPTION:
Mapping XS 0cb8970a
END DESCRIPTION:
XS GIS Cut Line= 3
      2781312.04     10241116.95      2780819.41     10239721.16
      2780290.48     10238809.22
#Sta/Elev= 30
  3934.1 1109.36  4144.3  1102.9  4365.8 1097.88  4436.6 1097.21  4489.6 1091.22
  4507.3 1094.53    4532 1093.72  4574.4 1086.76  4606.3 1086.64  4668.7 1079.53
  4802.6 1070.99  4860.8 1066.58  4892.6 1056.76  4960.6 1057.35  4966.3 1055.29
  4967.8 1054.29  5052.1 1055.29  5053.4 1057.25  5147.1 1060.11  5181.7 1066.73
  5274.3 1077.74  5347.7 1082.04  5562.3 1093.06  5731.7 1088.81  6042.2 1096.61
  6071.1 1096.37  6206.4 1095.95  6353.4  1100.4  6371.5 1101.14  6468.5 1105.16
#Mann= 14 ,-1 , 0
  3934.1     .05       0  4144.3     .12       0  4365.8     .05       0
  4668.7     .12       0  4802.6     .05       0  4966.3     .03       0
  5052.1     .05       0  5181.7     .12       0  5347.7     .05       0
  5731.7     .12       0  6042.2     .05       0  6071.1     .12       0
  6353.4     .05       0  6371.5     .12       0
Bank Sta=4966.3,5052.1
XS Rating Curve= 0 ,0
Exp/Cntr=0.3,0.1

Type RM Length L Ch R = 1 ,10579   ,1088,1088,1088
BEGIN DESCRIPTION:
Mapping XS 0e54836f
END DESCRIPTION:
XS GIS Cut Line= 2
      2782269.94     10240715.55      2781357.68     10238599.09
#Sta/Elev= 30
  3828.9 1093.83  3887.9 1094.02  4166.4 1095.01  4282.6 1090.24  4358.6 1092.65
  4505.2 1088.88  4639.1 1079.86  4715.1 1071.03  4784.7 1068.12  4862.5 1066.85
  4914.2 1063.65  4961.2 1053.26  4994.3 1053.06  4995.8 1052.06  5080.2 1053.06
  5083.8 1055.75  5095.2 1058.16  5181.8 1059.57  5241.8 1069.93  5274.9 1072.55
  5298.6 1074.51  5501.6  1085.6  5512.9 1085.51  5645.3 1094.86  5744.8 1097.97
  5780.8 1101.32  5813.4 1099.79    5857 1102.38  5952.7 1103.29  6133.6 1108.74
#Mann= 12 ,-1 , 0
  3828.9     .05       0  3887.9     .12       0  4166.4     .05       0
  4784.7     .12       0  4862.5     .05       0  4994.3     .03       0
  5080.2     .05       0  5274.9     .12       0  5298.6     .05       0
  5501.6     .12       0  5512.9     .05       0  5952.7     .12       0
Bank Sta=4994.3,5080.2
XS Rating Curve= 0 ,0
Exp/Cntr=0.3,0.1

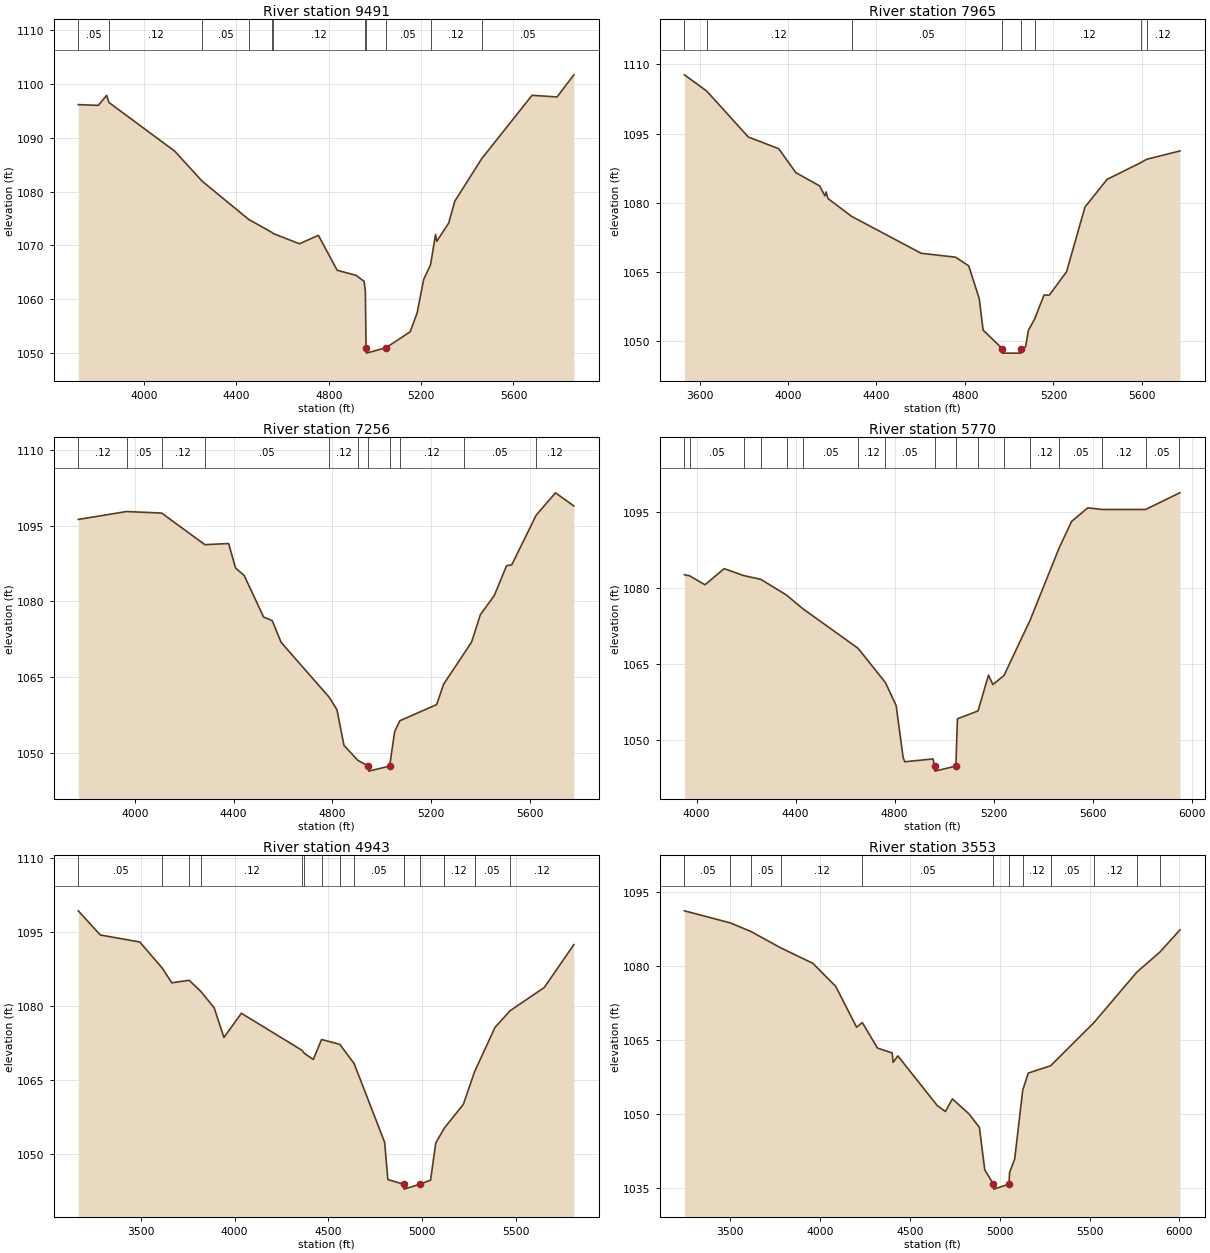
Type RM Length L Ch R = 1 ,9491    ,1526,1526,1526
BEGIN DESCRIPTION:
Mapping XS b0c8e361
END DESCRIPTION:
XS GIS Cut Line= 2
      2783027.15     10240633.48      2782616.81     10238527.08
#Sta/Elev= 30
  3715.5 1096.19    3802 1096.05  3838.1  1097.9  3848.2 1096.59  4133.6  1087.5
  4251.9 1081.92  4453.8 1074.79  4555.4 1072.35  4559.3 1072.18  4673.5 1070.26
  4755.1 1071.84  4836.6 1065.33  4918.1 1064.39    4953 1063.27  4958.6 1061.53
  4961.6 1050.89  4963.1 1049.89  5047.5 1050.89  5152.4 1053.85  5182.9 1057.38
    5211  1063.6    5241 1066.35  5262.7 1072.01  5267.8 1070.71  5319.4 1074.11
    5346  1078.2  5462.5 1086.12  5680.7 1097.93    5789 1097.62  5861.5 1101.74
#Mann= 11 ,-1 , 0
  3715.5     .05       0  3848.2     .12       0  4251.9     .05       0
  4453.8     .12       0  4555.4     .05       0  4559.3     .12       0
  4958.6     .05       0  4961.6     .03       0  5047.5     .05       0
    5241     .12       0  5462.5     .05       0
Bank Sta=4961.6,5047.5
XS Rating Curve= 0 ,0
Exp/Cntr=0.3,0.1

Type RM Length L Ch R = 1 ,7965    ,709,709,709
BEGIN DESCRIPTION:
Mapping XS 05781e5a
END DESCRIPTION:
XS GIS Cut Line= 2
      2783702.25     10240824.99      2784540.49     10238747.63
#Sta/Elev= 30
  3531.9 1107.73  3632.6 1104.21  3820.7 1094.24  3957.6 1091.72  4035.4 1086.52
  4142.8 1083.64  4166.9 1081.48  4172.3 1082.32  4180.9 1080.89  4287.7 1077.03
  4601.8 1069.03  4757.4 1068.18  4817.1  1066.3  4864.8 1059.15  4881.9 1052.38
  4968.3 1048.37  4969.8 1047.37  5052.8 1047.37  5054.3 1048.37  5074.1 1048.73
  5086.7 1052.29  5114.7 1054.75  5157.4 1059.96  5181.5 1059.95  5259.3 1065.03
  5342.5 1079.05  5442.6 1085.06  5593.9 1088.66  5621.8 1089.42    5772 1091.22
#Mann= 8 ,-1 , 0
  3531.9     .05       0  3632.6     .12       0  4287.7     .05       0
  4968.3     .03       0  5054.3     .05       0  5114.7     .12       0
  5593.9     .05       0  5621.8     .12       0
Bank Sta=4968.3,5054.3
XS Rating Curve= 0 ,0
Exp/Cntr=0.3,0.1

Type RM Length L Ch R = 1 ,7256    ,1486,1486,1486
BEGIN DESCRIPTION:
Mapping XS e17d21df
END DESCRIPTION:
XS GIS Cut Line= 2
      2784067.14     10240624.34      2785434.36     10239156.85
#Sta/Elev= 30
  3771.4 1096.28  3966.8 1097.85  4108.9 1097.54  4283.8 1091.27  4379.7  1091.5
    4408 1086.63  4443.2 1085.12  4521.4  1076.9  4556.5 1076.18  4592.2 1071.89
  4787.1 1060.97  4818.4 1058.49  4846.7 1051.43    4903 1048.45  4945.4 1047.32
  4946.9 1046.32  5031.4 1047.32  5051.9 1054.18  5072.8 1056.32  5221.8 1059.53
  5249.8 1063.55  5331.5 1069.59  5363.2 1071.94  5398.8 1077.38    5455 1081.16
  5504.8 1087.09  5525.8 1087.27  5624.9 1097.14  5702.7 1101.56  5777.1 1098.96
#Mann= 11 ,-1 , 0
  3771.4     .12       0  3966.8     .05       0  4108.9     .12       0
  4283.8     .05       0  4787.1     .12       0    4903     .05       0
  4945.4     .03       0  5031.4     .05       0  5072.8     .12       0
  5331.5     .05       0  5624.9     .12       0
Bank Sta=4945.4,5031.4
XS Rating Curve= 0 ,0
Exp/Cntr=0.3,0.1

Type RM Length L Ch R = 1 ,5770    ,827,827,827
BEGIN DESCRIPTION:
Mapping XS c0f8cfa4
END DESCRIPTION:
XS GIS Cut Line= 3
      2785389.99     10241144.32      2786247.52     10240387.13
      2786594.18     10239602.59
#Sta/Elev= 30
  3951.2 1082.56  3971.8 1082.36  4034.1 1080.59  4111.9 1083.77  4189.9 1082.41
  4259.6 1081.66  4363.8 1078.54  4429.2 1075.86  4652.5 1068.03  4763.1 1061.25
  4806.3 1056.72  4834.7 1046.42  4841.4  1045.6  4955.2 1046.16  4961.5 1044.75
    4963 1043.75  5047.6 1044.75  5053.9 1054.09  5137.1 1055.65  5179.4 1062.72
  5197.2 1060.86  5242.2 1062.67  5347.6  1073.6  5464.3 1087.81    5515  1093.1
  5580.6 1095.79  5638.1 1095.47  5813.9 1095.47  5948.1 1098.67  5952.9 1098.76
#Mann= 17 ,-1 , 0
  3951.2     .12       0  3971.8     .05       0  4189.9     .12       0
  4259.6     .05       0  4363.8     .12       0  4429.2     .05       0
  4652.5     .12       0  4763.1     .05       0  4961.5     .05       0
  5047.6     .05       0  5137.1     .12       0  5242.2     .05       0
  5347.6     .12       0  5464.3     .05       0  5638.1     .12       0
  5813.9     .05       0  5948.1     .12       0
Bank Sta=4961.5,5047.6
XS Rating Curve= 0 ,0
Exp/Cntr=0.3,0.1

Type RM Length L Ch R = 1 ,4943    ,1390,1390,1390
BEGIN DESCRIPTION:
Mapping XS 90a09c1f
END DESCRIPTION:
XS GIS Cut Line= 5
      2788090.37     10242047.51      2787324.02      10241609.6
      2786931.74     10241034.85      2786840.51     10240596.96
      2786612.45     10240022.25
#Sta/Elev= 30
    3166  1099.3  3283.3  1094.4  3493.9 1092.98  3614.7 1087.65  3664.8  1084.7
  3757.6 1085.21  3820.8 1082.91  3890.8 1079.63  3943.1 1073.62  4036.2 1078.52
  4358.2 1071.04    4372 1070.41  4419.7 1069.14  4463.9  1073.2  4561.2 1072.22
  4637.6 1068.33  4800.6 1052.34  4817.8 1044.79  4902.5 1043.85    4904 1042.85
  4988.8 1043.85  5045.7 1044.67  5073.2  1052.2  5117.9 1055.17  5220.6 1060.05
  5280.4 1066.66  5389.6 1075.67  5469.4 1079.02  5652.7 1083.76  5810.1 1092.44
#Mann= 14 ,-1 , 0
    3166     .05       0  3614.7     .12       0  3757.6     .05       0
  3820.8     .12       0  4358.2     .05       0    4372     .12       0
  4463.9     .05       0  4561.2     .12       0  4637.6     .05       0
  4902.5     .05       0  4988.8     .05       0  5117.9     .12       0
  5280.4     .05       0  5469.4     .12       0
Bank Sta=4902.5,4988.8
XS Rating Curve= 0 ,0
Exp/Cntr=0.3,0.1

Type RM Length L Ch R = 1 ,3553    ,910,910,910
BEGIN DESCRIPTION:
Mapping XS e87442ab
END DESCRIPTION:
XS GIS Cut Line= 3
      2788473.49     10241609.56      2788017.36     10240268.53
      2786794.89     10239721.16
#Sta/Elev= 30
  3247.2  1091.1    3502 1088.66  3614.6 1086.96  3782.4 1083.61  3961.7 1080.47
  4088.5 1075.81  4204.7 1067.55  4236.4 1068.49  4320.8 1063.32  4402.5 1062.34
  4407.8 1060.43  4433.9 1061.75  4653.5 1051.68  4698.4 1050.49  4737.4 1053.04
  4829.9    1050  4887.5 1047.28  4917.5 1038.67  4965.8 1035.78  4967.3 1034.78
  5052.1 1035.78  5055.4 1038.12    5084  1040.9  5128.4 1054.77  5159.1 1058.26
    5284 1059.76  5522.5 1068.39  5764.2 1078.73  5891.1 1082.74  6003.1 1087.25
#Mann= 12 ,-1 , 0
  3247.2     .05       0    3502     .12       0  3614.6     .05       0
  3782.4     .12       0  4236.4     .05       0  4965.8     .03       0
  5052.1     .05       0  5128.4     .12       0    5284     .05       0
  5522.5     .12       0  5764.2     .05       0  5891.1     .12       0
Bank Sta=4965.8,5052.1
XS Rating Curve= 0 ,0
Exp/Cntr=0.3,0.1

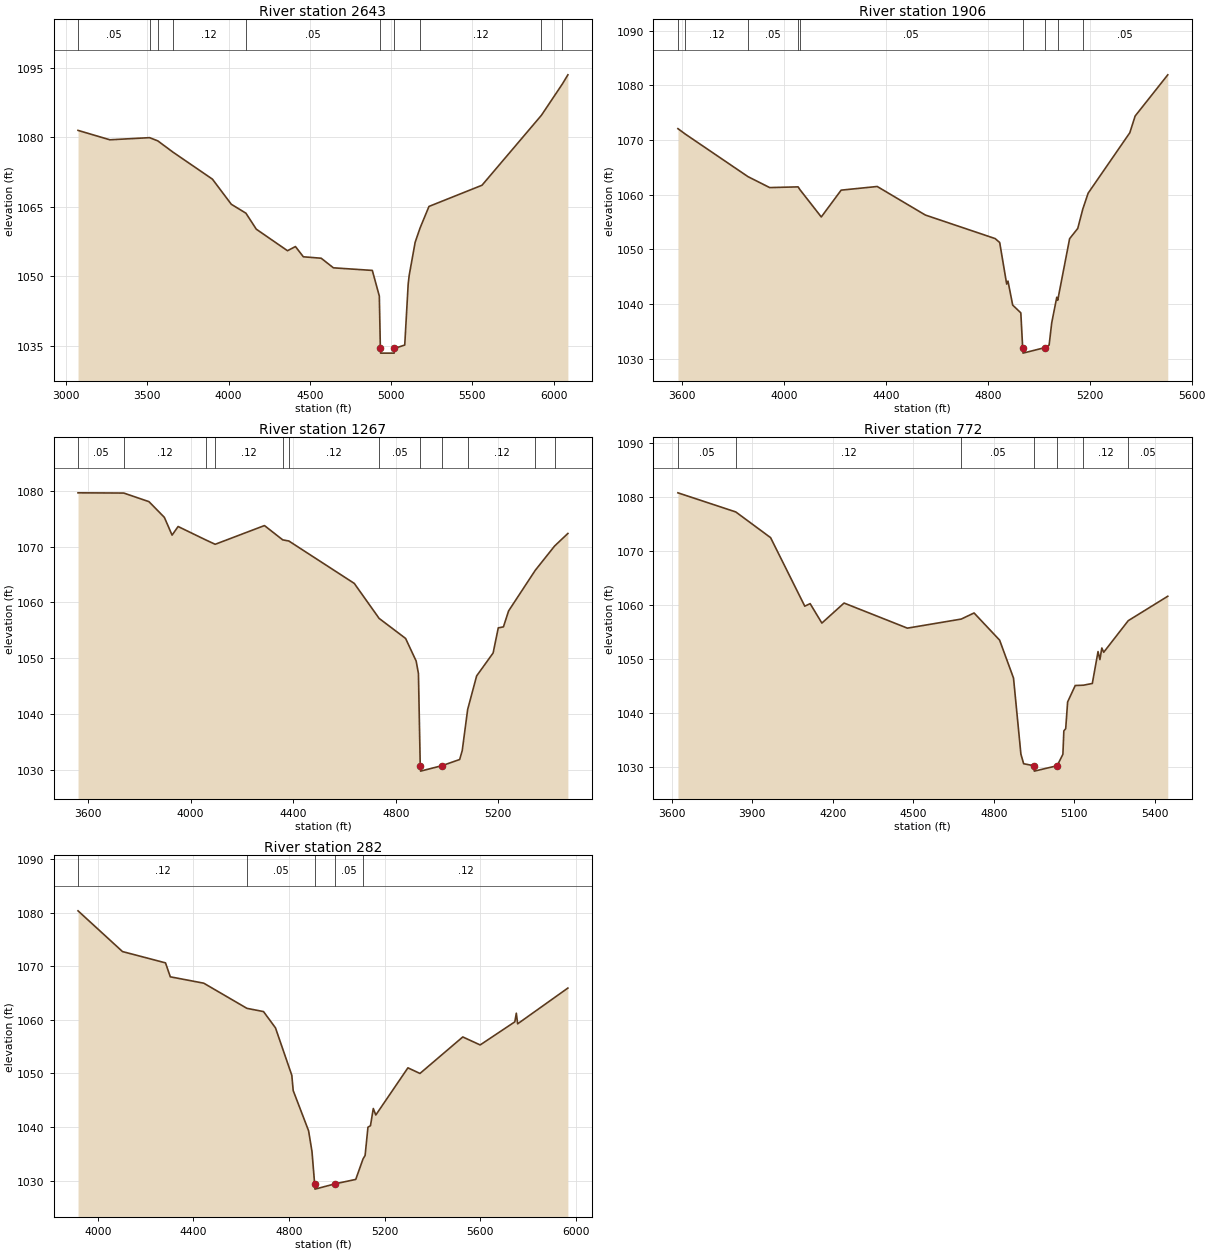
Type RM Length L Ch R = 1 ,2643    ,737,737,737
BEGIN DESCRIPTION:
Mapping XS 2393d62a
END DESCRIPTION:
XS GIS Cut Line= 3
      2788619.46     10241144.28      2788254.55     10239493.09
       2787223.7     10238662.93
#Sta/Elev= 30
    3073 1081.52  3268.8 1079.49  3513.6 1079.95  3564.3 1079.25  3655.4 1076.87
    3900    1071  4016.4 1065.57  4106.2 1063.65    4170  1060.2  4362.2 1055.55
    4411 1056.45  4459.7 1054.24  4569.4 1053.93  4644.6 1051.86  4884.1  1051.3
  4927.2 1045.76  4933.6 1034.45  4935.1 1033.45  5018.5 1033.45    5020 1034.45
  5083.6  1035.2  5104.8 1048.35  5111.2 1050.28  5147.8 1057.39  5178.3 1060.49
  5232.8 1065.11  5559.1 1069.68  5925.2  1084.8  6054.4 1091.58  6087.6 1093.51
#Mann= 10 ,-1 , 0
    3073     .05       0  3513.6     .12       0  3564.3     .05       0
  3655.4     .12       0  4106.2     .05       0  4933.6     .03       0
    5020     .05       0  5178.3     .12       0  5925.2     .05       0
  6054.4     .12       0
Bank Sta=4933.6,5020
XS Rating Curve= 0 ,0
Exp/Cntr=0.3,0.1

Type RM Length L Ch R = 1 ,1906    ,639,639,639
BEGIN DESCRIPTION:
Mapping XS 7a4ffad7
END DESCRIPTION:
XS GIS Cut Line= 3
      2788665.08     10240432.78      2788719.82     10239237.65
      2788574.07     10238527.13
#Sta/Elev= 30
  3584.6 1072.08  3613.2  1071.1  3859.4 1063.31  3944.6 1061.31  4056.2 1061.44
  4062.9 1060.95    4147 1055.94  4224.9 1060.84  4366.4 1061.51  4555.3 1056.29
    4829 1051.99  4846.9 1051.27  4874.3 1043.67  4879.4 1044.22  4897.9 1039.83
  4929.8 1038.41    4937 1032.05  4938.5 1031.05  5023.4 1032.05  5040.8 1032.51
    5051 1036.59  5070.8 1041.26  5074.5 1040.71  5121.2 1051.97  5153.1 1053.84
  5172.9 1057.38  5193.9 1060.29  5357.3 1071.33  5378.3 1074.39  5506.3 1081.92
#Mann= 9 ,-1 , 0
  3584.6     .05       0  3613.2     .12       0  3859.4     .05       0
  4056.2     .12       0  4062.9     .05       0    4937     .03       0
  5023.4     .05       0  5074.5     .12       0  5172.9     .05       0
Bank Sta=4937,5023.4
XS Rating Curve= 0 ,0
Exp/Cntr=0.3,0.1

Type RM Length L Ch R = 1 ,1267    ,495,495,495
BEGIN DESCRIPTION:
Mapping XS 4228ac74
END DESCRIPTION:
XS GIS Cut Line= 3
      2789267.19     10240569.54      2789312.81     10239255.89
      2789258.07     10238662.86
#Sta/Elev= 30
  3561.1 1079.62  3739.4 1079.58  3837.7 1078.04  3897.7 1075.23  3927.8 1072.05
  3951.3 1073.59  4060.1 1071.17  4095.9 1070.41    4288 1073.76  4359.3  1071.2
  4383.1    1071  4638.2 1063.41    4735 1057.15  4838.3 1053.56  4879.5 1049.51
  4888.4 1047.28  4895.4 1030.81  4896.9 1029.81  4981.8 1030.81  5049.1 1031.89
  5059.1 1033.47  5080.3 1040.84  5115.3 1046.85  5179.6 1050.96  5199.7 1055.45
  5219.8 1055.63  5239.9 1058.48  5343.7 1065.74  5419.1 1070.09  5471.1 1072.35
#Mann= 12 ,-1 , 0
  3561.1     .05       0  3739.4     .12       0  4060.1     .05       0
  4095.9     .12       0  4359.3     .05       0  4383.1     .12       0
    4735     .05       0  4895.4     .05       0  4981.8     .12       0
  5080.3     .12       0  5343.7     .05       0  5419.1     .12       0
Bank Sta=4895.4,4981.8
XS Rating Curve= 0 ,0
Exp/Cntr=0.3,0.1

Type RM Length L Ch R = 1 ,772     ,490,490,490
BEGIN DESCRIPTION:
Mapping XS 22f847f5
END DESCRIPTION:
XS GIS Cut Line= 4
      2789394.93     10240450.94      2789750.71     10239365.37
      2789805.44     10239082.56      2789531.76     10238799.75
#Sta/Elev= 30
  3623.8 1080.86  3839.2 1077.32  3968.8 1072.56  4096.1 1059.86  4116.1 1060.33
  4159.8 1056.73  4242.4 1060.44  4478.2 1055.79  4678.7 1057.47  4726.5  1058.6
  4821.6 1053.57  4873.4 1046.54  4900.9 1032.45  4911.1 1030.67  4949.4  1030.3
  4950.9  1029.3  5035.8  1030.3  5057.3 1032.42  5060.8 1036.75  5067.7 1037.17
  5074.9 1042.12  5103.2 1045.16  5133.7 1045.22  5166.8 1045.54  5188.1 1051.45
  5195.1 1049.96  5202.2 1052.11  5209.2 1051.32  5300.5 1057.17  5447.8  1061.7
#Mann= 7 ,-1 , 0
  3623.8     .05       0  3839.2     .12       0  4678.7     .05       0
  4949.4     .05       0  5035.8     .07       0  5133.7     .12       0
  5300.5     .05       0
Bank Sta=4949.4,5035.8
XS Rating Curve= 0 ,0
Exp/Cntr=0.3,0.1

Type RM Length L Ch R = 1 ,282     ,0,0,0
BEGIN DESCRIPTION:
Mapping XS 53c917d2
END DESCRIPTION:
XS GIS Cut Line= 4
      2790371.06     10240159.08      2790370.78     10239320.46
      2790282.25       10239093.      2789416.92     10238662.28
#Sta/Elev= 30
  3917.3 1080.33  4103.3 1072.73  4283.3 1070.62  4303.3 1068.02  4443.3 1066.83
  4623.8 1062.14  4693.3 1061.53  4743.3  1058.5  4811.7 1049.64  4817.5 1046.79
  4881.8  1039.3    4896 1035.45  4907.1 1029.41  4908.6 1028.41  4993.6 1029.41
  5079.1 1030.22  5109.6 1034.04  5118.3  1034.7  5130.2 1039.96  5140.7 1040.24
  5152.5 1043.45  5163.1 1042.24  5297.4 1051.04  5347.8 1049.99  5526.9  1056.8
  5599.7 1055.31  5744.6 1059.62  5750.9 1061.23  5756.4 1059.25  5966.6 1065.92
#Mann= 5 ,-1 , 0
  3917.3     .12       0  4623.8     .05       0  4907.1     .05       0
  4993.6     .05       0  5109.6     .12       0
Bank Sta=4907.1,4993.6
XS Rating Curve= 0 ,0
Exp/Cntr=0.3,0.1
Stream Node=SAN FERNANDO CRE,Reach-1         , 0 , 0 ,Upstream end
Stream Node=SAN FERNANDO CRE,Reach-1         , 0 , 1 ,Downstream end

Chan Stop Cuts=-1
Use User Specified Reach Order=0
Composite Channel Slope=5