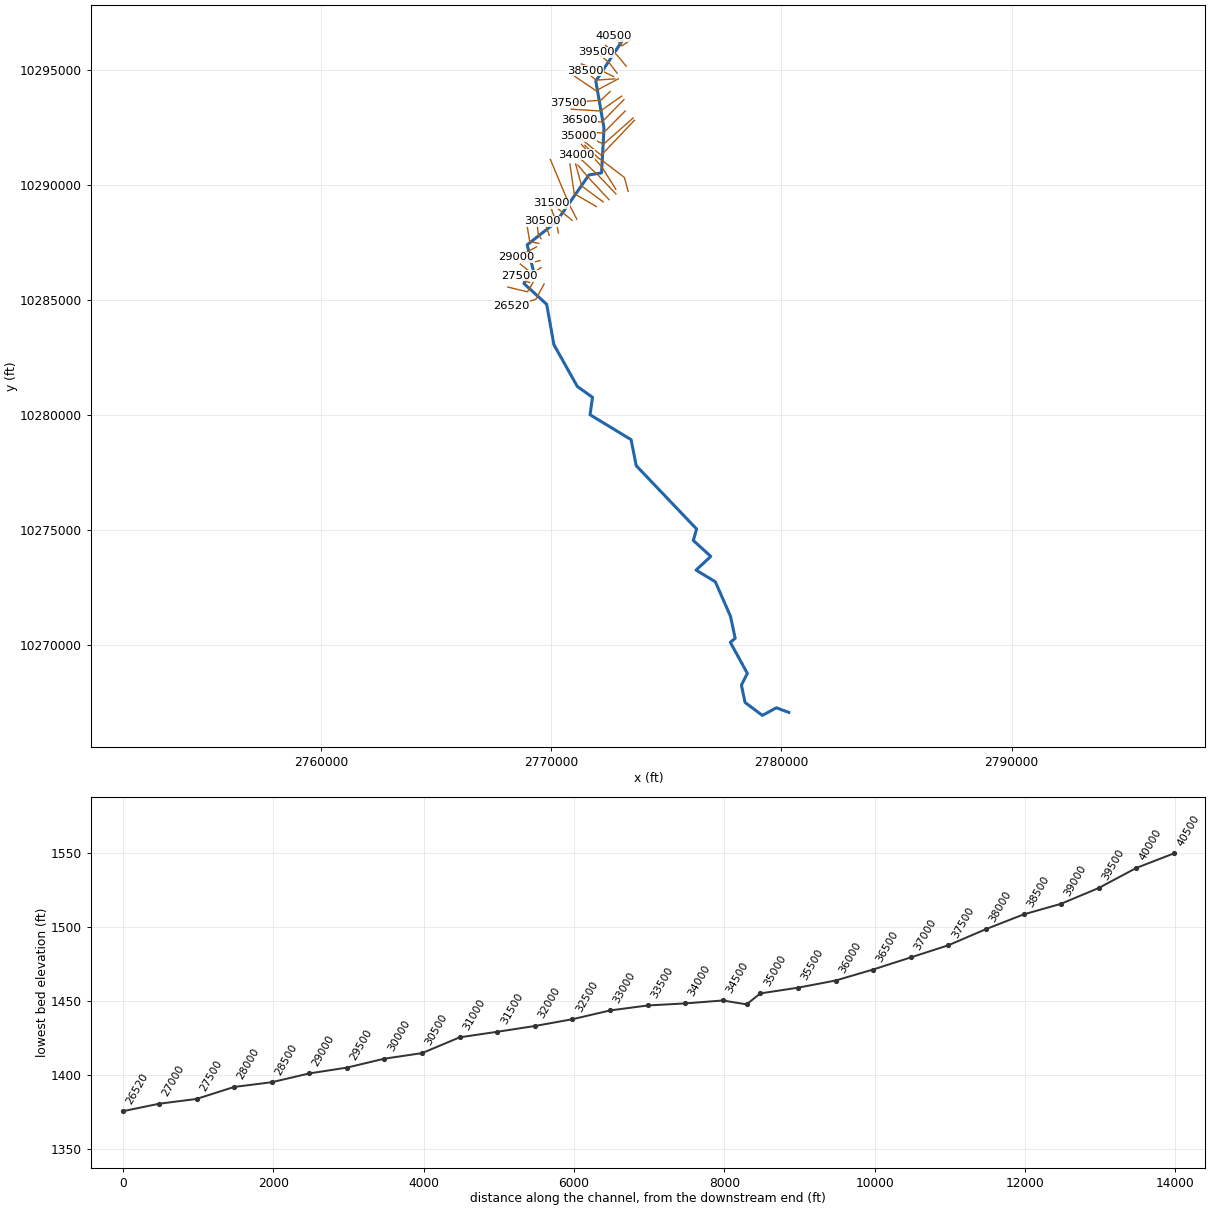
--- SAND SPRING CREEK.prj (project) ---

Proj Title=SAND SPRING CREEK Base Level Engineering
Current Plan=p01
Default Exp/Contr=0.3,0.1
English Units
Geom File=g01
Flow File=f01
Plan File=p01
Y Axis Title=Elevation
X Axis Title(PF)=Main Channel Distance
X Axis Title(XS)=Station
BEGIN DESCRIPTION:
SAND SPRING CREEK
END DESCRIPTION:
DSS Export Rating Curves= 0
DSS Export Rating Curve Sorted= 0
DSS Export Volume Flow Curves= 0
DXF OffsetX= 0
DXF OffsetY= 0
DXF ScaleX= 1
DXF ScaleY= 10

--- SAND SPRING CREEK.p01 (plan) ---

Plan Title=Multiple Run
Short Identifier=Multiple
Geom File=g01
Flow File=f01
Subcritical Flow
K Sum by GR= 0
Std Step Tol= 0.01
Critical Tol= 0.01
Num of Std Step Trials= 20
Max Error Tol= 0.3
Flow Tol Ratio= 0.001
Split Flow NTrial= 30
Split Flow Tol= 0.02
Split Flow Ratio= 0.02
Log Output Level= 0
Friction Slope Method= 1
Unsteady Friction Slope Method= 2
Unsteady Bridges Friction Slope Method= 1
Parabolic Critical Depth
Global Vel Dist=  1 , 1 , 1
Global Log Level= 0
CheckData=True
Encroach Param= -1, 0, 0, 0
BEGIN DESCRIPTION:
Multiple Run
END DESCRIPTION:

--- SAND SPRING CREEK.f01 (steady flow) ---

Flow Title=Multiple
Number of Profiles=7
Profile Names=10-year,25-year,50-year,1pct_min,100-year,1pct_plu,500-year
River Rch & RM= SAND SPRING CREE,Reach-1,40500
     477     775    1676    1234    2374    4567    3465
River Rch & RM= SAND SPRING CREE,Reach-1,31500
     809    1369    2778    1734    3976    9117    5752
River Rch & RM= SAND SPRING CREE,Reach-1,24000
    1135    1966    4018    2510    5816   13480    8401
River Rch & RM= SAND SPRING CREE,Reach-1,17500
    1358    2379    4905    4072    7141   12523   10292
River Rch & RM= SAND SPRING CREE,Reach-1,14000
    1678    2986    5910    4955    8627   15019   12373
River Rch & RM= SAND SPRING CREE,Reach-1,7500
    1939    3497    6578    5058    9608   18250   13736
Boundary for River Rch & Prof#=SAND SPRING CREE,Reach-1,1
Up Type=0
Dn Type=3
Dn Slope=0.005
Boundary for River Rch & Prof#=SAND SPRING CREE,Reach-1,2
Up Type=0
Dn Type=3
Dn Slope=0.005
Boundary for River Rch & Prof#=SAND SPRING CREE,Reach-1,3
Up Type=0
Dn Type=3
Dn Slope=0.005
Boundary for River Rch & Prof#=SAND SPRING CREE,Reach-1,4
Up Type=0
Dn Type=3
Dn Slope=0.005
Boundary for River Rch & Prof#=SAND SPRING CREE,Reach-1,5
Up Type=0
Dn Type=3
Dn Slope=0.005
Boundary for River Rch & Prof#=SAND SPRING CREE,Reach-1,6
Up Type=0
Dn Type=3
Dn Slope=0.005
Boundary for River Rch & Prof#=SAND SPRING CREE,Reach-1,7
Up Type=0
Dn Type=3
Dn Slope=0.005

--- SAND SPRING CREEK.g01 (geometry) ---

Geom Title=Existing Conditions
Program Version=4.10

River Reach=SAND SPRING CREE,Reach-1
Reach XY= 30
      2773084.25       10296265.      2771932.25       10294506.
       2772288.5       10292454.        2772181.       10290516.
        2771634.       10290426.        2770202.       10288375.
      2768949.75       10287390.      2769207.25       10286300.
      2768802.75       10285711.      2769795.75       10284805.
        2770111.       10283049.      2771128.25       10281233.
        2771789.       10280761.      2771682.25       10280004.
      2773463.75       10278923.       2773689.5       10277789.
        2776311.       10275039.       2776170.5       10274541.
        2776929.       10273846.       2776288.5       10273251.
        2777127.       10272746.      2777786.75       10271242.
      2777989.75       10270286.        2777778.       10270114.
      2778519.25       10268761.      2778260.75       10268253.
      2778418.75       10267499.       2779170.5       10266935.
      2779777.25       10267266.      2780326.25       10267064.

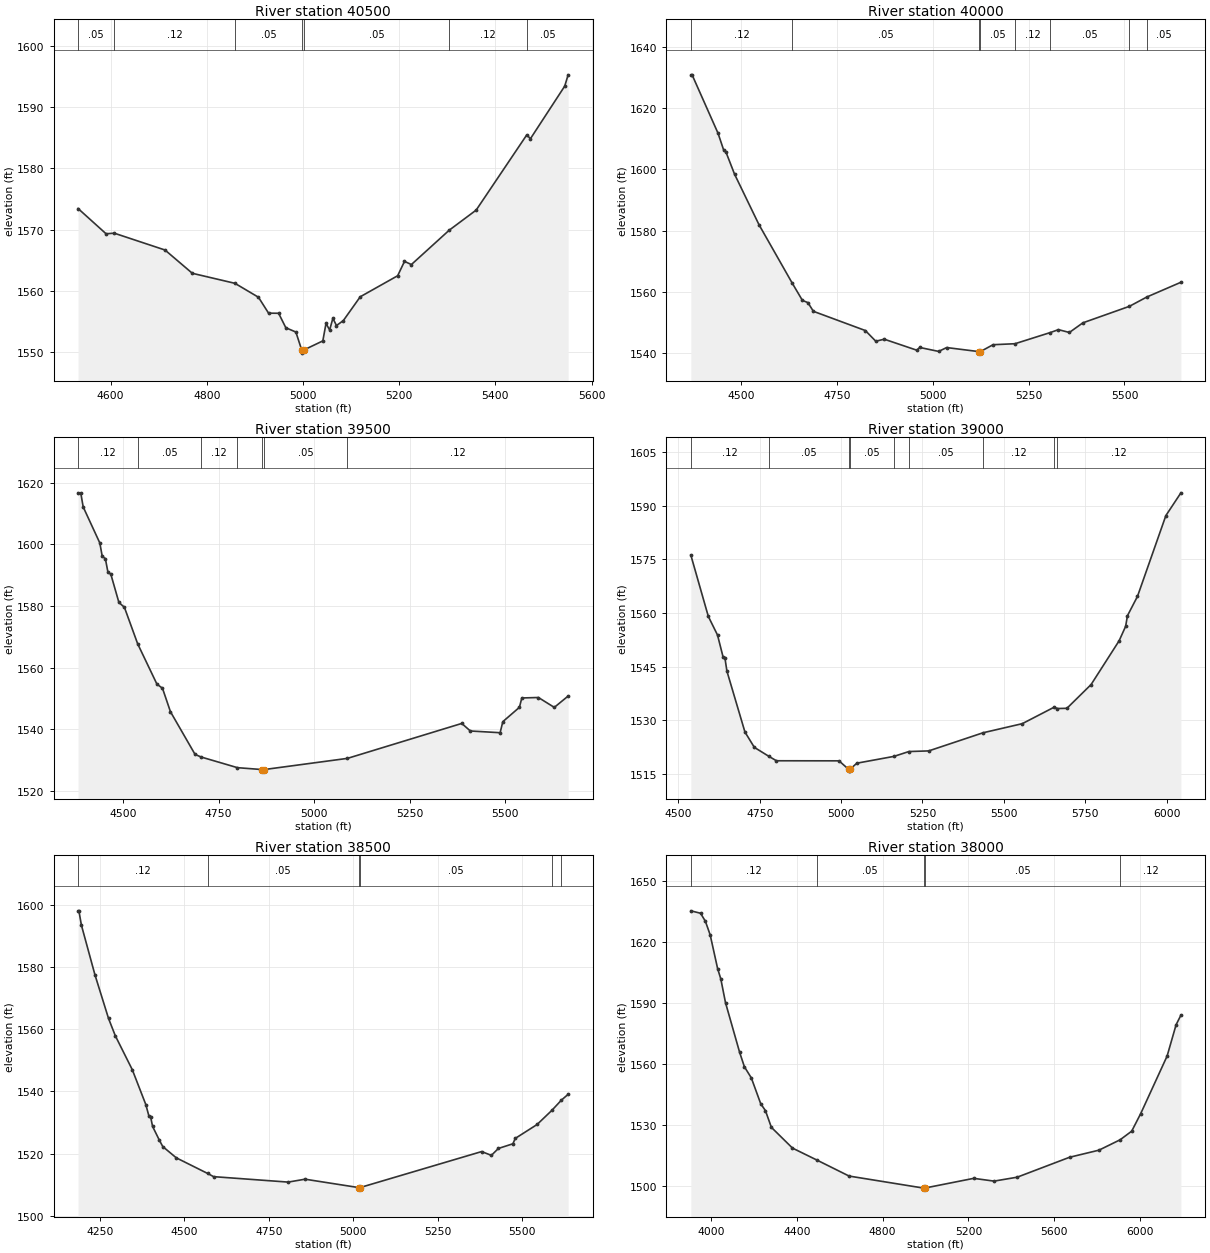
Type RM Length L Ch R = 1 ,40500   ,500,500,500
BEGIN DESCRIPTION:
SAND SPRING CREEK 80.0
END DESCRIPTION:
XS GIS Cut Line= 3
      2773455.64     10296303.08      2773069.82     10296039.09
      2772705.66     10296453.13
#Sta/Elev= 30
  4532.5 1573.45  4590.7 1569.32  4607.9 1569.41  4713.3 1566.66  4770.1 1562.85
  4858.7 1561.21  4907.6 1558.93  4928.6 1556.33  4949.5 1556.31  4964.5 1553.94
  4985.4 1553.24  4997.5 1550.29  4997.7 1549.79  5001.5 1550.29  5041.4 1551.79
    5048 1554.64  5055.6 1553.58  5062.3 1555.49  5069.8  1554.3  5084.1 1555.12
  5119.2 1559.01    5197 1562.45  5211.2  1564.8  5225.5 1564.28  5304.3 1569.91
  5360.2 1573.19  5465.3 1585.48  5473.1 1584.88  5544.3 1593.47  5551.4 1595.32
#Mann= 7 ,-1 , 0
  4532.5     .05       0  4607.9     .12       0  4858.7     .05       0
  4997.5     .05       0  5001.5     .05       0  5304.3     .12       0
  5465.3     .05       0
Bank Sta=4997.5,5001.5
XS Rating Curve= 0 ,0
Exp/Cntr=0.3,0.1

Type RM Length L Ch R = 1 ,40000   ,500,500,500
BEGIN DESCRIPTION:
SAND SPRING CREEK 79.0
END DESCRIPTION:
XS GIS Cut Line= 3
      2773255.71     10295153.08      2772851.83     10295637.63
      2772355.71     10296053.09
#Sta/Elev= 30
  4369.2 1630.88  4372.5 1630.88  4440.2 1611.78  4454.5 1606.43    4461 1605.59
  4483.1 1598.46  4546.9 1581.93  4633.4 1562.87  4660.2 1557.18  4674.5 1556.46
  4688.8 1553.62  4824.2 1547.34  4851.5 1543.85  4873.6 1544.51  4958.3 1540.92
  4966.1 1541.81  5015.4 1540.52  5036.3 1541.78  5120.1 1540.46  5120.4 1539.96
  5124.1 1540.46  5157.3 1542.71  5214.4 1543.03  5306.7 1546.69  5327.7 1547.63
  5356.3 1546.71  5391.5 1549.86  5512.8 1555.25  5558.3  1558.3  5647.1 1563.11
#Mann= 8 ,-1 , 0
  4369.2     .12       0  4633.4     .05       0  5120.1     .05       0
  5124.1     .05       0  5214.4     .12       0  5306.7     .05       0
  5512.8     .12       0  5558.3     .05       0
Bank Sta=5120.1,5124.1
XS Rating Curve= 0 ,0
Exp/Cntr=0.3,0.1

Type RM Length L Ch R = 1 ,39500   ,500,500,500
BEGIN DESCRIPTION:
SAND SPRING CREEK 78.0
END DESCRIPTION:
XS GIS Cut Line= 3
      2772855.66     10294853.14      2772478.75     10295342.52
      2771955.66     10295753.13
#Sta/Elev= 30
  4382.3 1616.76  4389.5 1616.65  4395.8 1612.17  4439.3 1600.48  4445.6 1596.15
  4453.8 1595.39  4460.2 1591.22  4468.3 1590.26  4489.2 1581.19  4503.7 1579.58
  4538.4 1567.73  4588.8 1554.65  4603.3 1553.32  4624.1 1545.72  4688.5 1531.86
  4704.2 1531.01  4799.6 1527.54    4865 1526.92  4865.2 1526.42    4869 1526.92
  5087.4 1530.56  5386.6  1541.9  5409.1 1539.45    5487 1538.89  5494.1 1542.48
  5537.5 1547.13  5543.8 1550.17  5587.2 1550.32  5628.8 1547.11    5665 1550.79
#Mann= 7 ,-1 , 0
  4382.3     .12       0  4538.4     .05       0  4704.2     .12       0
  4799.6     .05       0    4865     .05       0    4869     .05       0
  5087.4     .12       0
Bank Sta=4865,4869
XS Rating Curve= 0 ,0
Exp/Cntr=0.3,0.1

Type RM Length L Ch R = 1 ,39000   ,500,500,500
BEGIN DESCRIPTION:
SAND SPRING CREEK 77.0
END DESCRIPTION:
XS GIS Cut Line= 3
      2772705.64     10294703.13      2772289.43     10294902.97
      2771305.69     10295253.11
#Sta/Elev= 30
  4538.3 1576.24  4592.1 1559.06  4620.3 1553.86  4637.4 1547.72  4642.9 1547.57
  4649.2 1543.76  4704.6 1526.71  4733.5 1522.42  4778.1 1519.91  4801.4 1518.67
  4993.7 1518.65  5023.2 1516.27  5023.5 1515.77  5027.2 1516.27  5048.4 1517.99
  5162.6  1519.9  5208.3 1521.25  5269.3 1521.43  5436.4 1526.51  5556.7 1529.05
  5654.4 1533.65  5664.9 1533.29  5693.9 1533.35  5768.2    1540  5854.4 1552.26
  5874.4 1556.31  5879.9 1559.26  5910.8 1564.69    5998 1587.29  6044.2 1593.66
#Mann= 9 ,-1 , 0
  4538.3     .12       0  4778.1     .05       0  5023.2     .05       0
  5027.2     .05       0  5162.6     .12       0  5208.3     .05       0
  5436.4     .12       0  5654.4     .05       0  5664.9     .12       0
Bank Sta=5023.2,5027.2
XS Rating Curve= 0 ,0
Exp/Cntr=0.3,0.1

Type RM Length L Ch R = 1 ,38500   ,500,500,500
BEGIN DESCRIPTION:
SAND SPRING CREEK 76.0
END DESCRIPTION:
XS GIS Cut Line= 3
      2772755.65     10294603.11      2771943.26     10294545.89
      2771455.66     10294953.13
#Sta/Elev= 30
  4185.6 1597.99  4188.1 1597.99  4195.6 1593.36  4235.7 1577.39  4275.8  1563.4
  4295.8 1557.85    4346 1546.95  4386.1 1535.73  4395.1  1532.1  4400.1 1531.86
  4406.1 1528.71  4426.2 1524.27  4436.2 1522.24  4476.3 1518.61  4568.7 1513.61
  4586.6 1512.57  4807.1 1510.82  4857.2 1511.75  5015.7 1509.06    5016 1508.56
  5019.7 1509.06  5379.5 1520.63  5408.2 1519.41    5429 1521.63  5471.9 1523.13
  5478.9 1524.86  5543.5 1529.33  5586.9 1533.84  5615.4 1537.16  5635.3 1539.03
#Mann= 6 ,-1 , 0
  4185.6     .12       0  4568.7     .05       0  5015.7     .05       0
  5019.7     .05       0  5586.9     .12       0  5615.4     .05       0
Bank Sta=5015.7,5019.7
XS Rating Curve= 0 ,0
Exp/Cntr=0.3,0.1

Type RM Length L Ch R = 1 ,38000   ,500,500,500
BEGIN DESCRIPTION:
SAND SPRING CREEK 75.0
END DESCRIPTION:
XS GIS Cut Line= 3
      2772905.66      10294603.1      2771941.95      10294086.8
      2770955.72     10294753.08
#Sta/Elev= 30
  3906.7 1635.19  3952.1    1634  3974.7 1630.03  3996.9 1623.37  4031.5 1606.87
  4046.4 1601.78  4068.3 1590.12  4134.1 1565.76  4156.3 1558.67  4188.6 1553.21
  4232.4 1540.53  4254.4 1537.14    4282 1528.95  4380.3 1518.77  4492.3 1512.99
  4644.1 1505.04  4991.7 1499.13  4991.9 1498.63  4995.7 1499.13  5224.8 1503.92
  5319.6 1502.56  5427.5 1504.49  5671.3 1514.26  5808.1 1517.74  5906.9 1522.84
  5960.9 1527.07  6002.9 1535.69  6125.8  1563.9  6167.8  1579.3  6190.2 1583.98
#Mann= 5 ,-1 , 0
  3906.7     .12       0  4492.3     .05       0  4991.7     .05       0
  4995.7     .05       0  5906.9     .12       0
Bank Sta=4991.7,4995.7
XS Rating Curve= 0 ,0
Exp/Cntr=0.3,0.1

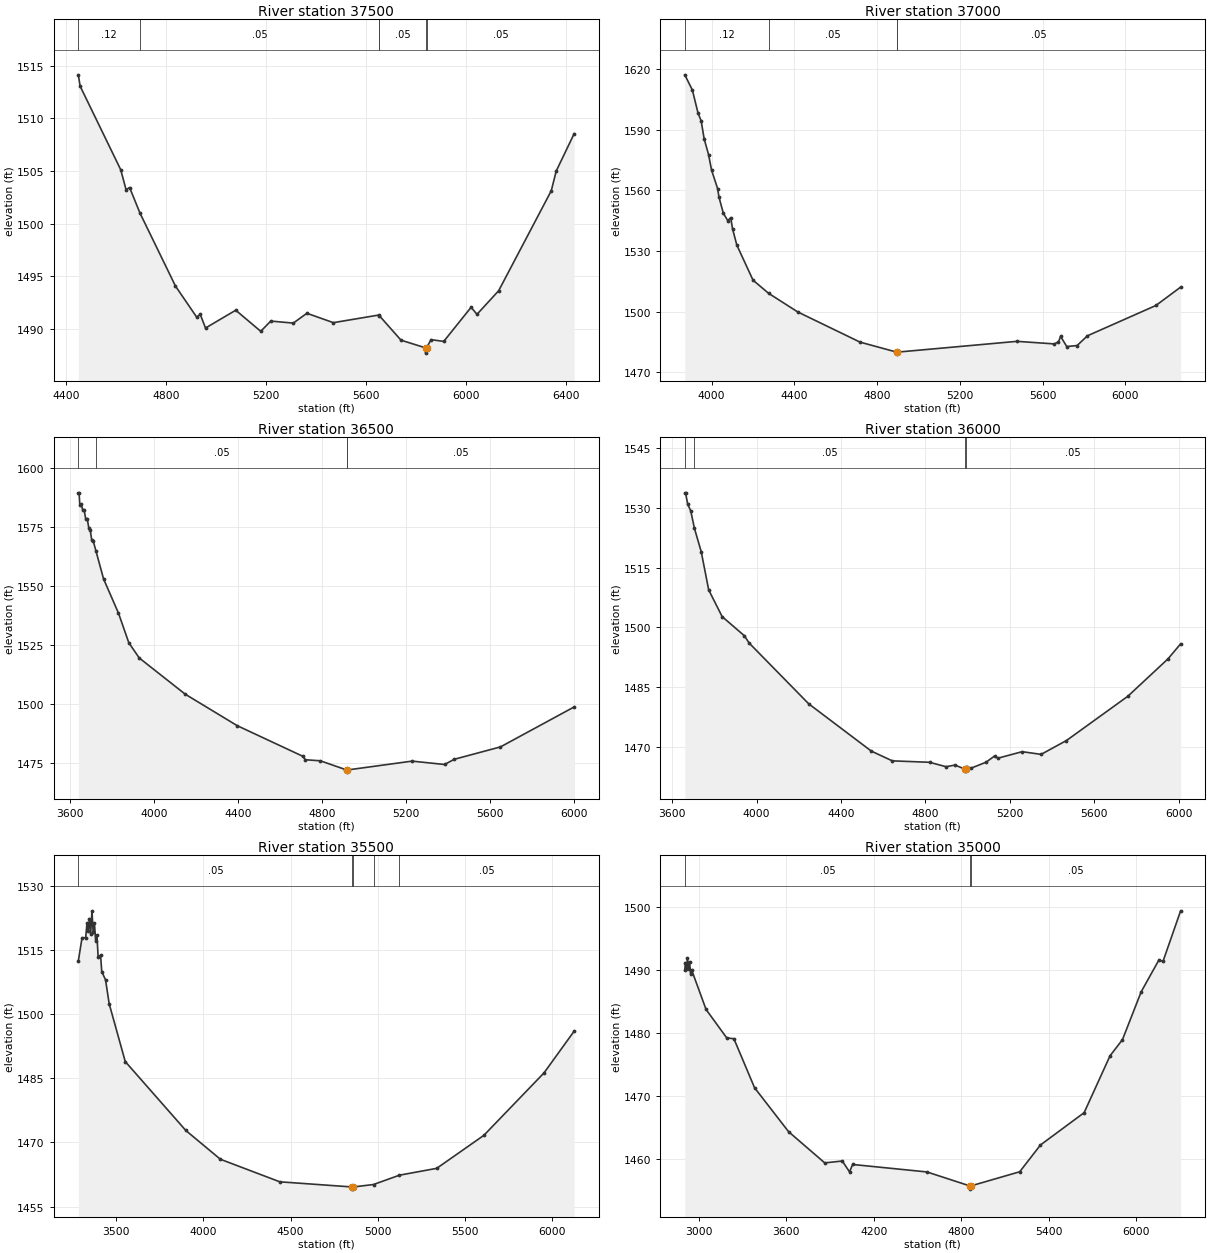
Type RM Length L Ch R = 1 ,37500   ,500,500,500
BEGIN DESCRIPTION:
SAND SPRING CREEK 74.0
END DESCRIPTION:
XS GIS Cut Line= 3
      2772555.67      10294053.1      2772153.33     10293674.73
      2770724.21     10293569.39
#Sta/Elev= 30
  4447.7 1514.13  4454.8 1513.06  4617.4 1505.13  4638.9 1503.23    4653 1503.44
  4694.8    1501  4836.7 1494.09  4921.7 1491.14  4935.8 1491.41  4956.9 1490.11
  5077.9  1491.8  5178.1  1489.8  5218.2 1490.77  5308.5 1490.58  5362.9 1491.51
  5468.9 1490.62  5649.9 1491.34  5653.4 1491.27  5739.6 1488.96  5837.9 1488.23
  5838.2 1487.73  5841.9 1488.23    5860 1489.01  5910.7 1488.84  6020.4 1492.08
  6043.9 1491.41  6130.7 1493.65  6341.3 1503.13  6361.3 1505.01    6433 1508.55
#Mann= 6 ,-1 , 0
  4447.7     .12       0  4694.8     .05       0  5649.9     .12       0
  5653.4     .05       0  5837.9     .05       0  5841.9     .05       0
Bank Sta=5837.9,5841.9
XS Rating Curve= 0 ,0
Exp/Cntr=0.3,0.1

Type RM Length L Ch R = 1 ,37000   ,500,500,500
BEGIN DESCRIPTION:
SAND SPRING CREEK 73.0
END DESCRIPTION:
XS GIS Cut Line= 3
      2773055.71     10293853.13      2772130.65     10293205.19
      2770866.46     10293284.88
#Sta/Elev= 30
  3870.6 1617.21  3907.3 1609.66  3934.7 1598.22  3949.5  1594.5  3964.3 1585.47
  3985.3 1577.79  4000.1 1570.02  4029.3  1560.9  4035.8 1556.68  4056.8 1548.76
  4078.2 1545.09  4092.5 1546.56  4101.2 1541.09  4122.1 1532.97  4200.3 1515.63
  4275.7 1509.11  4416.8 1499.88  4717.6 1484.97  4894.3 1480.03  4894.6 1479.53
  4898.3 1480.03  5475.9 1485.36  5656.3 1484.09  5676.3  1485.1  5686.8 1487.81
  5716.4 1482.79  5766.5 1483.29  5816.6 1488.12  6147.2  1503.1  6266.7 1512.18
#Mann= 4 ,-1 , 0
  3870.6     .12       0  4275.7     .05       0  4894.3     .05       0
  4898.3     .05       0
Bank Sta=4894.3,4898.3
XS Rating Curve= 0 ,0
Exp/Cntr=0.3,0.1

Type RM Length L Ch R = 1 ,36500   ,500,500,500
BEGIN DESCRIPTION:
SAND SPRING CREEK 72.0
END DESCRIPTION:
XS GIS Cut Line= 3
      2773155.69     10293703.12      2772203.47     10292730.28
      2771205.73     10292803.11
#Sta/Elev= 30
  3638.7 1589.34  3642.2 1589.34  3645.8 1584.22  3652.8 1584.51  3659.9 1581.96
  3666.9 1581.87  3674.1 1578.12  3681.1  1578.4  3688.2 1574.61  3695.2 1573.66
  3702.4 1569.36  3709.4 1568.99  3722.9  1564.6  3758.9 1552.85  3829.7 1538.39
  3879.1 1525.81  3928.7 1519.35  4147.8 1503.99  4395.3 1490.65  4706.5 1477.72
  4720.6 1476.19  4791.3 1475.75  4916.6 1471.87  4916.9 1471.37  4920.6 1471.87
  5228.4 1475.61  5383.1 1474.18  5428.9 1476.38  5649.5 1481.64  6000.4 1498.58
#Mann= 4 ,-1 , 0
  3638.7     .12       0  3722.9     .05       0  4916.6     .05       0
  4920.6     .05       0
Bank Sta=4916.6,4920.6
XS Rating Curve= 0 ,0
Exp/Cntr=0.3,0.1

Type RM Length L Ch R = 1 ,36000   ,500,500,500
BEGIN DESCRIPTION:
SAND SPRING CREEK 71.0
END DESCRIPTION:
XS GIS Cut Line= 3
      2773205.68     10293203.11      2772263.51     10292250.69
      2771255.67     10292303.11
#Sta/Elev= 30
  3660.3 1533.81  3663.8 1533.81  3674.4  1530.9  3688.5 1529.28  3705.9  1524.9
  3738.1 1519.03  3773.4 1509.45  3837.1 1502.73  3943.1 1497.89  3964.4 1496.13
  4247.2 1480.83  4544.2 1468.94  4643.2  1466.5    4820 1466.14  4897.8 1465.03
  4940.2 1465.44  4987.7 1464.42  4987.9 1463.92  4991.7 1464.42  4994.9 1465.03
  5017.8 1464.69  5087.9 1466.17    5128 1467.73    5143 1467.16  5258.2  1468.8
  5348.3 1468.13  5468.5 1471.61  5758.8 1482.71  5949.1  1492.1  6009.2 1495.88
#Mann= 4 ,-1 , 0
  3660.3     .12       0  3705.9     .05       0  4987.7     .05       0
  4991.7     .05       0
Bank Sta=4987.7,4991.7
XS Rating Curve= 0 ,0
Exp/Cntr=0.3,0.1

Type RM Length L Ch R = 1 ,35500   ,500,500,500
BEGIN DESCRIPTION:
SAND SPRING CREEK 70.0
END DESCRIPTION:
XS GIS Cut Line= 3
      2773555.66     10292903.09      2772269.65     10291765.73
       2771255.7      10292253.1
#Sta/Elev= 30
  3283.2 1512.42  3304.5 1517.83  3325.4 1517.85  3332.9 1521.33  3339.6 1519.34
  3347.2 1522.31  3353.8 1518.73  3361.4 1524.13  3368.1 1519.19  3375.6 1521.17
  3382.3 1517.17  3389.8 1518.47  3396.5 1513.44  3410.7 1513.73  3417.4 1509.94
  3439.2 1507.99  3460.1 1502.39  3552.1  1488.9  3899.2 1472.79  4097.5 1466.06
  4437.9 1460.79  4854.2 1459.58  4854.4 1459.08  4858.2 1459.58    4975 1460.16
  5123.9 1462.34  5337.3 1463.94  5607.4 1471.65  5952.5 1486.26    6125 1496.01
#Mann= 5 ,-1 , 0
  3283.2     .05       0  4854.2     .07       0  4858.2     .05       0
    4975     .12       0  5123.9     .05       0
Bank Sta=4854.2,4858.2
XS Rating Curve= 0 ,0
Exp/Cntr=0.3,0.1

Type RM Length L Ch R = 1 ,35000   ,184,184,184
BEGIN DESCRIPTION:
SAND SPRING CREEK 69.0
END DESCRIPTION:
XS GIS Cut Line= 3
       2773612.2      10292802.4      2772169.71     10291284.21
      2771155.69     10292103.11
#Sta/Elev= 30
  2905.8    1490  2909.9 1491.21  2917.1 1490.25    2924 1491.94  2931.3 1490.25
  2938.2 1491.37  2945.4 1489.47  2952.3 1490.08  3051.4 1483.78    3193 1479.26
  3242.3 1479.12  3383.9 1471.33  3617.3 1464.34  3864.8 1459.39    3985 1459.69
  4034.7 1457.96  4055.8 1459.14    4565 1457.95  4860.3 1455.72  4860.6 1455.22
  4864.3 1455.72  5200.8 1457.98  5343.1 1462.24  5642.2 1467.37  5819.7 1476.41
  5904.9 1478.98  6033.5  1486.6  6153.9 1491.61  6182.7 1491.42  6303.4 1499.45
#Mann= 3 ,-1 , 0
  2905.8     .05       0  4860.3     .05       0  4864.3     .05       0
Bank Sta=4860.3,4864.3
XS Rating Curve= 0 ,0
Exp/Cntr=0.3,0.1

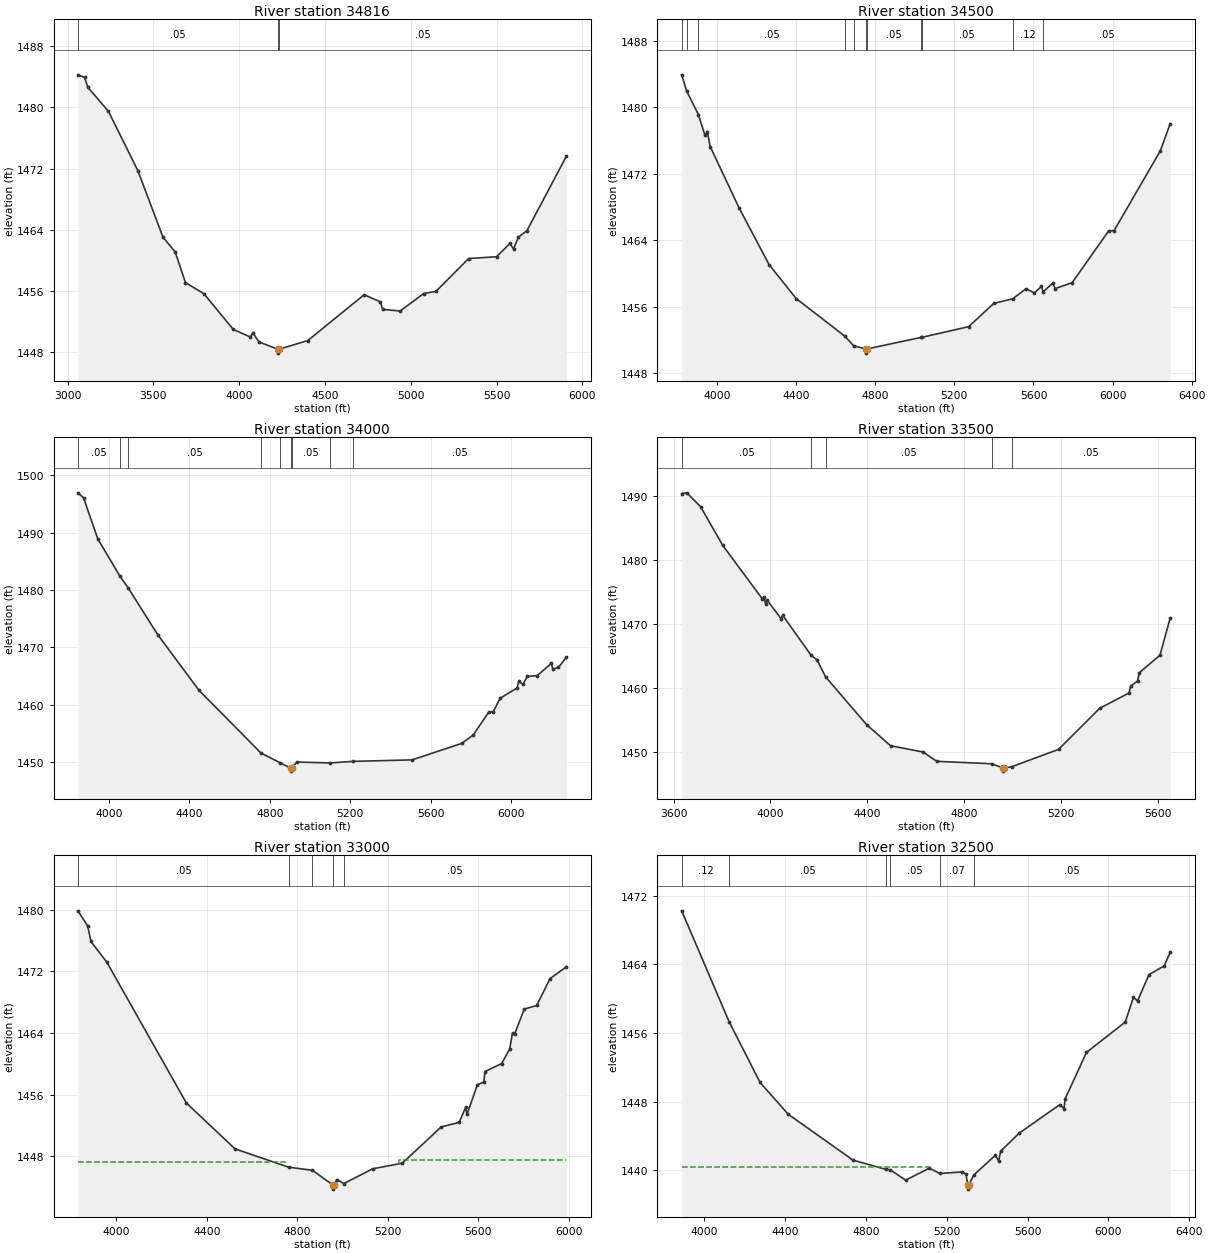
Type RM Length L Ch R = 1 ,34816   ,316,316,316
BEGIN DESCRIPTION:
Mapping XS cc4775a7
END DESCRIPTION:
XS GIS Cut Line= 5
      2773336.49     10289715.59      2773174.84     10290316.93
      2772211.38     10291054.06      2772069.13     10291138.12
      2771449.55     10291712.53
#Sta/Elev= 30
  3060.9 1484.28  3099.8 1483.94  3118.5 1482.65  3238.4  1479.5  3410.4  1471.7
  3555.4 1463.05  3627.9 1461.04  3687.2 1457.06  3795.1 1455.59  3965.6 1450.93
  4065.3 1449.93  4079.8 1450.49  4115.2 1449.28  4227.4 1448.32  4227.7 1447.82
  4231.4 1448.32  4400.2 1449.47  4728.1 1455.47  4821.5 1454.55  4836.1 1453.55
  4938.2 1453.34    5075 1455.63  5145.9  1455.9  5336.9 1460.21  5499.7 1460.45
  5577.3 1462.19  5598.4 1461.46  5626.7    1463  5676.6 1463.87  5906.8 1473.63
#Mann= 3 ,-1 , 0
  3060.9     .05       0  4227.4     .05       0  4231.4     .05       0
Bank Sta=4227.4,4231.4
XS Rating Curve= 0 ,0
Exp/Cntr=0.3,0.1

Type RM Length L Ch R = 1 ,34500   ,500,500,500
BEGIN DESCRIPTION:
SAND SPRING CREEK 68.0
END DESCRIPTION:
XS GIS Cut Line= 3
      2772805.66     10289803.15      2772176.88      10290799.9
      2771305.65     10291753.14
#Sta/Elev= 30
  3821.5 1483.88  3847.6 1481.88  3905.9  1479.1  3938.5 1476.66  3951.5 1476.99
  3965.6 1475.26  4111.5  1467.9  4263.4 1461.07  4400.8 1456.99  4646.3 1452.48
  4691.1 1451.31  4753.5 1450.94  4753.8 1450.44  4757.5 1450.94    5034 1452.34
  5034.3 1452.33  5272.3 1453.62  5399.3 1456.41  5495.2 1456.97  5562.1 1458.17
  5604.7 1457.68  5640.4 1458.46    5649  1457.8  5696.5 1458.84  5710.7  1458.2
  5795.8 1458.91  5979.8 1465.11    6008 1465.17  6241.7 1474.75  6291.4 1478.01
#Mann= 11 ,-1 , 0
  3821.5     .05       0  3847.6     .12       0  3905.9     .05       0
  4646.3     .12       0  4691.1     .05       0  4753.5     .05       0
  4757.5     .05       0    5034     .12       0  5034.3     .05       0
  5495.2     .12       0    5649     .05       0
Bank Sta=4753.5,4757.5
XS Rating Curve= 0 ,0
Exp/Cntr=0.3,0.1

Type RM Length L Ch R = 1 ,34000   ,500,500,500
BEGIN DESCRIPTION:
SAND SPRING CREEK 67.0
END DESCRIPTION:
XS GIS Cut Line= 3
      2772805.69      10289603.1      2772009.88     10290440.05
      2771073.89     10291307.14
#Sta/Elev= 30
  3845.1 1496.94  3873.2 1496.04    3944  1488.9  4052.8 1482.48  4096.5  1480.3
  4241.3 1472.26  4446.4 1462.58  4755.5 1451.62  4851.3 1449.91  4904.2 1448.96
  4904.5 1448.46  4908.2 1448.96  4934.6 1450.05  5097.6 1449.88  5212.3 1450.16
  5507.7 1450.42  5755.5  1453.3  5811.6 1454.74  5889.9 1458.77  5910.8 1458.78
  5946.3 1461.16    6031 1462.96  6038.4 1464.12  6059.4 1463.57  6080.9 1464.95
  6130.3  1465.1  6201.1 1467.24  6207.9 1466.22  6236.3 1466.54  6275.9 1468.29
#Mann= 9 ,-1 , 0
  3845.1     .05       0  4052.8     .12       0  4096.5     .05       0
  4755.5     .12       0  4851.3     .05       0  4904.2     .05       0
  4908.2     .05       0  5097.6     .12       0  5212.3     .05       0
Bank Sta=4904.2,4908.2
XS Rating Curve= 0 ,0
Exp/Cntr=0.3,0.1

Type RM Length L Ch R = 1 ,33500   ,500,500,500
BEGIN DESCRIPTION:
SAND SPRING CREEK 66.0
END DESCRIPTION:
XS GIS Cut Line= 3
      2772505.66     10289353.14      2771573.61     10290352.98
      2771155.66     10290853.14
#Sta/Elev= 30
  3633.1 1490.35  3654.3 1490.47    3711 1488.31  3802.8 1482.27  3965.5 1473.97
  3972.9 1474.29  3979.7 1473.17    3987  1473.7  4043.2 1470.87  4050.5 1471.37
  4167.7 1465.14  4192.2 1464.43  4227.7 1461.77  4397.4 1454.31  4496.1 1451.03
  4630.9 1450.05  4687.1  1448.6  4913.8 1448.22  4961.1 1447.57  4961.4 1447.07
  4965.1 1447.57  4996.7 1447.75  5190.4 1450.46  5360.9 1456.88  5481.9 1459.26
  5488.4 1460.31  5517.1 1461.12  5523.6  1462.4  5609.5 1465.14  5651.8 1470.93
#Mann= 5 ,-1 , 0
  3633.1     .05       0  4167.7     .12       0  4227.7     .05       0
  4913.8     .07       0  4996.7     .05       0
Bank Sta=4961.1,4965.1
XS Rating Curve= 0 ,0
Exp/Cntr=0.3,0.1

Type RM Length L Ch R = 1 ,33000   ,500,500,500
BEGIN DESCRIPTION:
SAND SPRING CREEK 65.0
END DESCRIPTION:
XS GIS Cut Line= 3
      2772255.66     10289253.13      2771314.93     10289948.59
      2771055.68     10290903.12
#Sta/Elev= 30
  3830.1 1479.87  3872.9 1477.91  3887.5 1475.89  3958.4 1473.16  4309.2  1454.9
  4524.2 1448.94  4761.5 1446.56  4866.1 1446.16  4958.5 1444.21  4958.8 1443.71
  4962.5 1444.21  4974.2 1444.96  5004.9 1444.43  5132.4 1446.35  5263.7 1447.08
  5435.3 1451.79  5514.9 1452.38  5543.5 1454.32  5549.5 1453.41  5595.3 1457.26
  5623.9 1457.64  5629.1 1458.99  5702.9 1460.03  5738.2  1461.9  5750.8 1464.03
  5761.1 1463.93  5802.6  1467.1  5857.6 1467.57  5916.6 1471.06  5989.1  1472.6
#Mann= 5 ,-1 , 0
  3830.1     .05       0  4761.5     .12       0  4866.1     .05       0
  4958.5     .07       0  5004.9     .05       0
#XS Ineff= 2 , 0
         4745.74 1447.24    5250         1447.43
Permanent Ineff=
       F       F
Bank Sta=4958.5,4962.5
XS Rating Curve= 0 ,0
Exp/Cntr=0.3,0.1

Type RM Length L Ch R = 1 ,32500   ,500,500,500
BEGIN DESCRIPTION:
SAND SPRING CREEK 64.0
END DESCRIPTION:
XS GIS Cut Line= 3
      2771955.72     10289053.09      2770994.25     10289611.38
      2770805.69     10290903.08
#Sta/Elev= 30
  3888.2 1470.26  4122.6 1457.33  4276.1 1450.23  4415.2 1446.52  4736.4 1441.16
  4898.7 1440.09  4918.6 1440.05  4996.8 1438.83  5112.9 1440.22  5165.8 1439.61
  5274.6 1439.78  5294.8 1439.54  5303.8 1438.28  5304.1 1437.78  5307.8 1438.28
  5335.3 1439.47  5440.7 1441.74  5456.5 1441.06  5466.6 1442.21  5557.6  1444.3
  5759.7 1447.65  5779.9 1447.18  5785.6 1448.32  5891.1 1453.73  6083.1 1457.28
  6123.5 1460.17  6143.7 1459.74  6200.4 1462.81  6275.5 1463.83  6305.4 1465.42
#Mann= 6 ,-1 , 0
  3888.2     .12       0  4122.6     .05       0  4898.7     .12       0
  4918.6     .05       0  5165.8     .07       0  5335.3     .05       0
#XS Ineff= 2 , 0
         5115.91 1440.38
Permanent Ineff=
       F       F
Bank Sta=5303.8,5307.8
XS Rating Curve= 0 ,0
Exp/Cntr=0.3,0.1

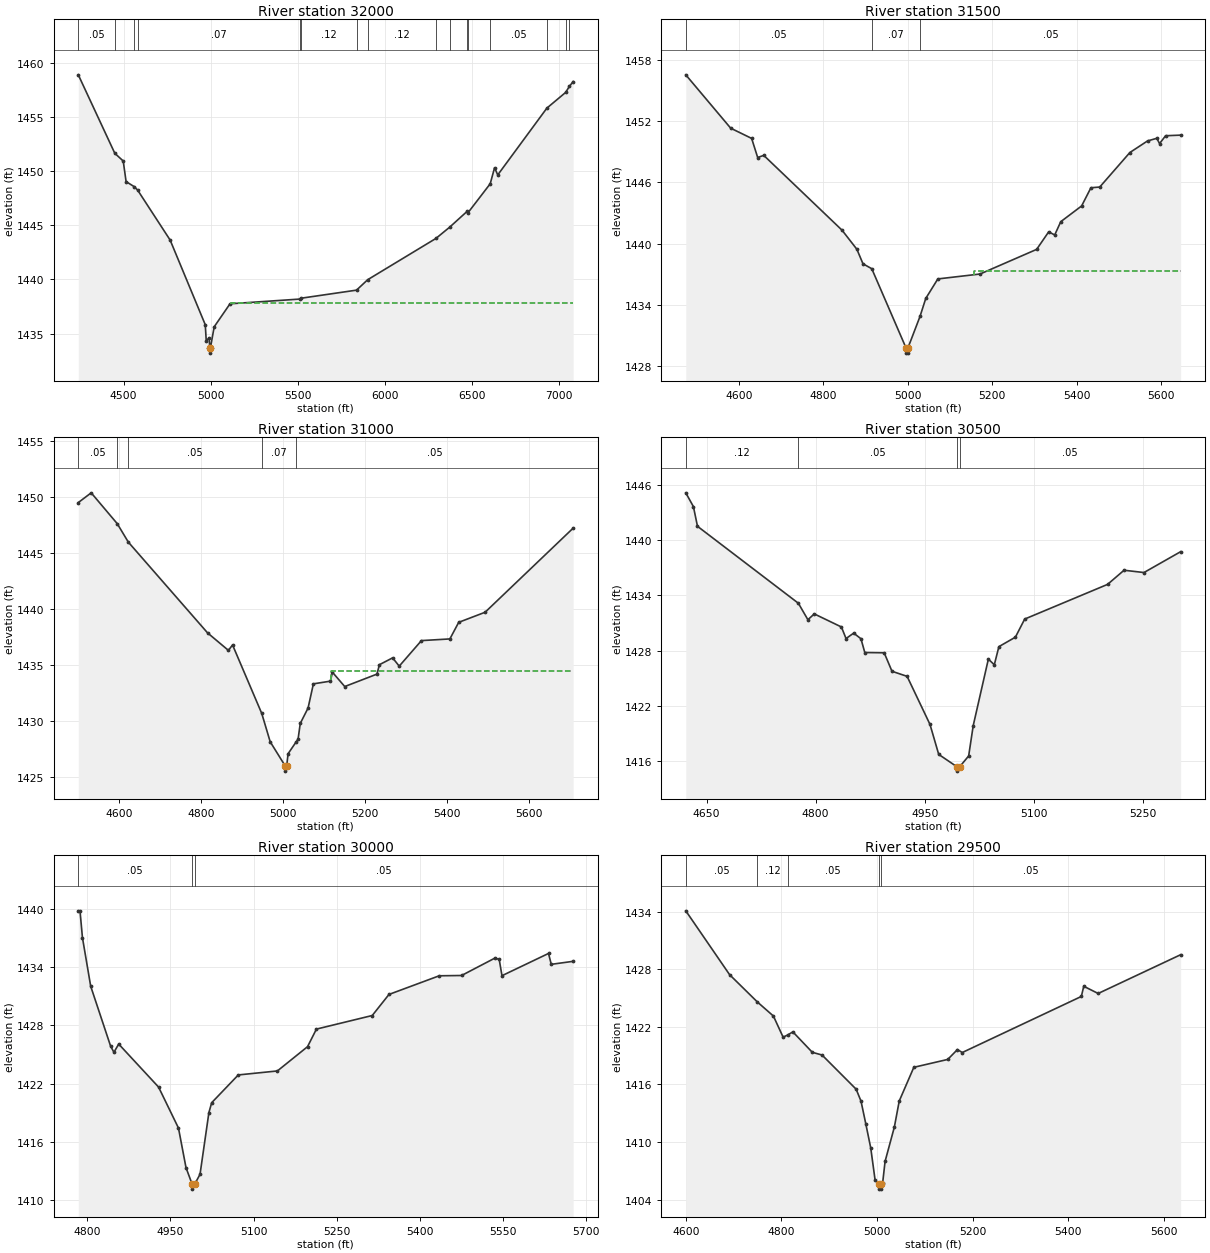
Type RM Length L Ch R = 1 ,32000   ,500,500,500
BEGIN DESCRIPTION:
SAND SPRING CREEK 63.0
END DESCRIPTION:
XS GIS Cut Line= 3
      2771105.67     10288503.15      2770758.99     10289180.48
      2769955.68     10291103.11
#Sta/Elev= 30
  4239.1 1458.87  4449.1 1451.63  4497.4 1450.92  4513.9 1449.02  4562.1 1448.54
  4580.5 1448.23    4767 1443.63    4969 1435.82  4974.6 1434.33  4991.2 1434.62
  4994.8  1433.7  4995.1  1433.2  4998.8  1433.7  5020.3 1435.63  5111.2 1437.75
    5516 1438.19    5522 1438.27  5838.5 1439.01  5902.4 1439.97  6294.9 1443.78
  6373.2 1444.81  6474.4 1446.28  6477.2 1446.11  6606.8 1448.82  6631.8  1450.3
  6650.2 1449.64  6932.6  1455.8  7040.6 1457.25  7062.1 1457.81  7083.7 1458.25
#Mann= 16 ,-1 , 0
  4239.1     .05       0  4449.1     .12       0  4562.1     .05       0
  4580.5     .07       0    5516     .05       0    5522     .12       0
  5838.5     .05       0  5902.4     .12       0  6294.9     .05       0
  6373.2     .12       0  6474.4     .05       0  6477.2     .12       0
  6606.8     .05       0  6932.6     .12       0  7040.6     .05       0
  7062.1     .12       0
#XS Ineff= 2 , 0
                          5119.6         1437.82
Permanent Ineff=
       F       F
Bank Sta=4994.8,4998.8
XS Rating Curve= 0 ,0
Exp/Cntr=0.3,0.1

Type RM Length L Ch R = 1 ,31500   ,500,500,500
BEGIN DESCRIPTION:
SAND SPRING CREEK 62.0
END DESCRIPTION:
XS GIS Cut Line= 3
      2770905.68     10288453.11      2770497.74     10288784.53
      2770005.69     10289203.11
#Sta/Elev= 30
  4474.4 1456.53  4580.7 1451.31  4630.3 1450.31  4644.6 1448.44    4659 1448.65
  4844.3 1441.33  4879.5 1439.46  4893.9 1438.04  4914.7 1437.56  4995.9  1429.8
  4996.2  1429.3    5000  1429.3  5000.3  1429.8    5029  1432.9  5042.5 1434.65
  5071.1 1436.56    5171 1437.04    5305 1439.45  5333.6 1441.17  5347.8 1440.86
  5362.1 1442.16  5411.5  1443.7  5433.5 1445.48  5454.4 1445.55  5525.8 1448.93
  5567.5 1450.06  5589.5 1450.32    5596  1449.8  5610.3 1450.57    5646 1450.63
#Mann= 3 ,-1 , 0
  4474.4     .05       0  4914.7     .07       0    5029     .05       0
#XS Ineff= 2 , 0
                         5155.68         1437.33
Permanent Ineff=
       F       F
Bank Sta=4995.9,5000.3
XS Rating Curve= 0 ,0
Exp/Cntr=0.3,0.1

Type RM Length L Ch R = 1 ,31000   ,500,500,500
BEGIN DESCRIPTION:
SAND SPRING CREEK 61.0
END DESCRIPTION:
XS GIS Cut Line= 3
      2770305.69     10287903.08      2770213.98      10288394.6
      2769955.67     10289053.15
#Sta/Elev= 30
    4500 1449.52  4531.5 1450.39    4595 1447.64  4622.1 1445.99  4815.4 1437.89
  4866.2 1436.33  4876.4 1436.81  4947.6  1430.7  4968.2 1428.17  5004.2 1426.05
  5004.5 1425.55  5008.6 1426.05  5011.8  1427.1  5030.6 1428.11  5036.2  1428.4
  5041.6 1429.81  5060.6 1431.18  5073.6 1433.34  5114.9 1433.58  5120.2 1434.37
  5150.1  1433.1  5228.7 1434.21  5234.7 1435.05  5266.9 1435.66    5283 1434.92
  5337.2  1437.2  5406.6 1437.35  5428.1 1438.83  5492.5 1439.73  5707.4 1447.24
#Mann= 5 ,-1 , 0
    4500     .05       0    4595     .12       0  4622.1     .05       0
  4947.6     .07       0  5030.6     .05       0
#XS Ineff= 2 , 0
                         5115.36         1434.48
Permanent Ineff=
       F       F
Bank Sta=5004.2,5008.6
XS Rating Curve= 0 ,0
Exp/Cntr=0.3,0.1

Type RM Length L Ch R = 1 ,30500   ,500,500,500
BEGIN DESCRIPTION:
SAND SPRING CREEK 60.0
END DESCRIPTION:
XS GIS Cut Line= 3
      2769905.68     10287803.11      2769790.14     10288163.75
      2769605.67     10288403.12
#Sta/Elev= 30
  4621.3 1445.16  4631.8 1443.66  4637.4 1441.52  4776.2 1433.15  4789.3 1431.36
  4798.1 1431.99  4835.4 1430.57  4841.8 1429.31  4852.3  1429.9  4862.3 1429.29
  4867.6 1427.79  4894.3 1427.76    4905 1425.75  4925.8  1425.2  4957.3 1419.97
  4969.3 1416.71  4993.9 1415.39  4994.2 1414.89  4998.4 1415.39  5010.5 1416.54
  5016.8 1419.85  5037.6 1427.07  5045.8 1426.46  5052.1 1428.43  5074.8 1429.46
  5087.6 1431.43  5201.6  1435.2  5224.3 1436.74  5251.7 1436.49  5302.2 1438.76
#Mann= 4 ,-1 , 0
  4621.3     .12       0  4776.2     .05       0  4993.9     .05       0
  4998.4     .05       0
Bank Sta=4993.9,4998.4
XS Rating Curve= 0 ,0
Exp/Cntr=0.3,0.1

Type RM Length L Ch R = 1 ,30000   ,500,500,500
BEGIN DESCRIPTION:
SAND SPRING CREEK 59.0
END DESCRIPTION:
XS GIS Cut Line= 3
      2769555.71     10287653.07      2769433.18     10287831.08
      2769355.68     10288503.12
#Sta/Elev= 30
  4783.9  1439.8    4787  1439.8  4791.4 1437.04  4806.3 1432.03  4842.1 1425.88
  4848.2 1425.23  4856.8 1426.08  4928.7 1421.65  4964.6 1417.43  4978.2 1413.35
  4989.3 1411.64  4989.6 1411.14  4993.8 1411.64  5003.5 1412.67  5019.5 1419.03
  5024.5 1420.04  5072.5  1422.9    5143 1423.31  5197.4 1425.81  5213.4 1427.62
  5314.1 1429.02  5344.3 1431.19  5434.9 1433.11  5475.2 1433.14  5535.6 1434.94
  5543.1 1434.79  5548.1 1433.12    5632 1435.41    5637 1434.29  5676.5  1434.6
#Mann= 3 ,-1 , 0
  4783.9     .05       0  4989.3     .05       0  4993.8     .05       0
Bank Sta=4989.3,4993.8
XS Rating Curve= 0 ,0
Exp/Cntr=0.3,0.1

Type RM Length L Ch R = 1 ,29500   ,500,500,500
BEGIN DESCRIPTION:
SAND SPRING CREEK 58.0
END DESCRIPTION:
XS GIS Cut Line= 3
      2769455.68     10287453.11      2769062.83     10287527.32
      2768955.68     10288153.11
#Sta/Elev= 30
  4600.2 1434.08  4691.8 1427.43    4750 1424.58  4783.4 1423.12  4803.7 1420.92
  4813.4 1421.15  4824.1 1421.47  4864.8 1419.34  4885.1 1419.06  4956.4  1415.5
  4966.6 1414.25  4976.7 1411.86  4986.9 1409.38    4996 1406.04  5003.5 1405.59
  5003.8 1405.09  5007.9 1405.09  5008.3 1405.59  5011.8 1405.73  5016.9 1407.98
  5036.3 1411.56  5046.5 1414.27    5077 1417.78  5147.9  1418.6  5168.2 1419.63
  5178.3 1419.32  5427.2 1425.16  5432.3 1426.22  5462.4 1425.47  5634.9 1429.51
#Mann= 5 ,-1 , 0
  4600.2     .05       0    4750     .12       0  4813.4     .05       0
  5003.5     .05       0  5008.3     .05       0
Bank Sta=5003.5,5008.3
XS Rating Curve= 0 ,0
Exp/Cntr=0.3,0.1

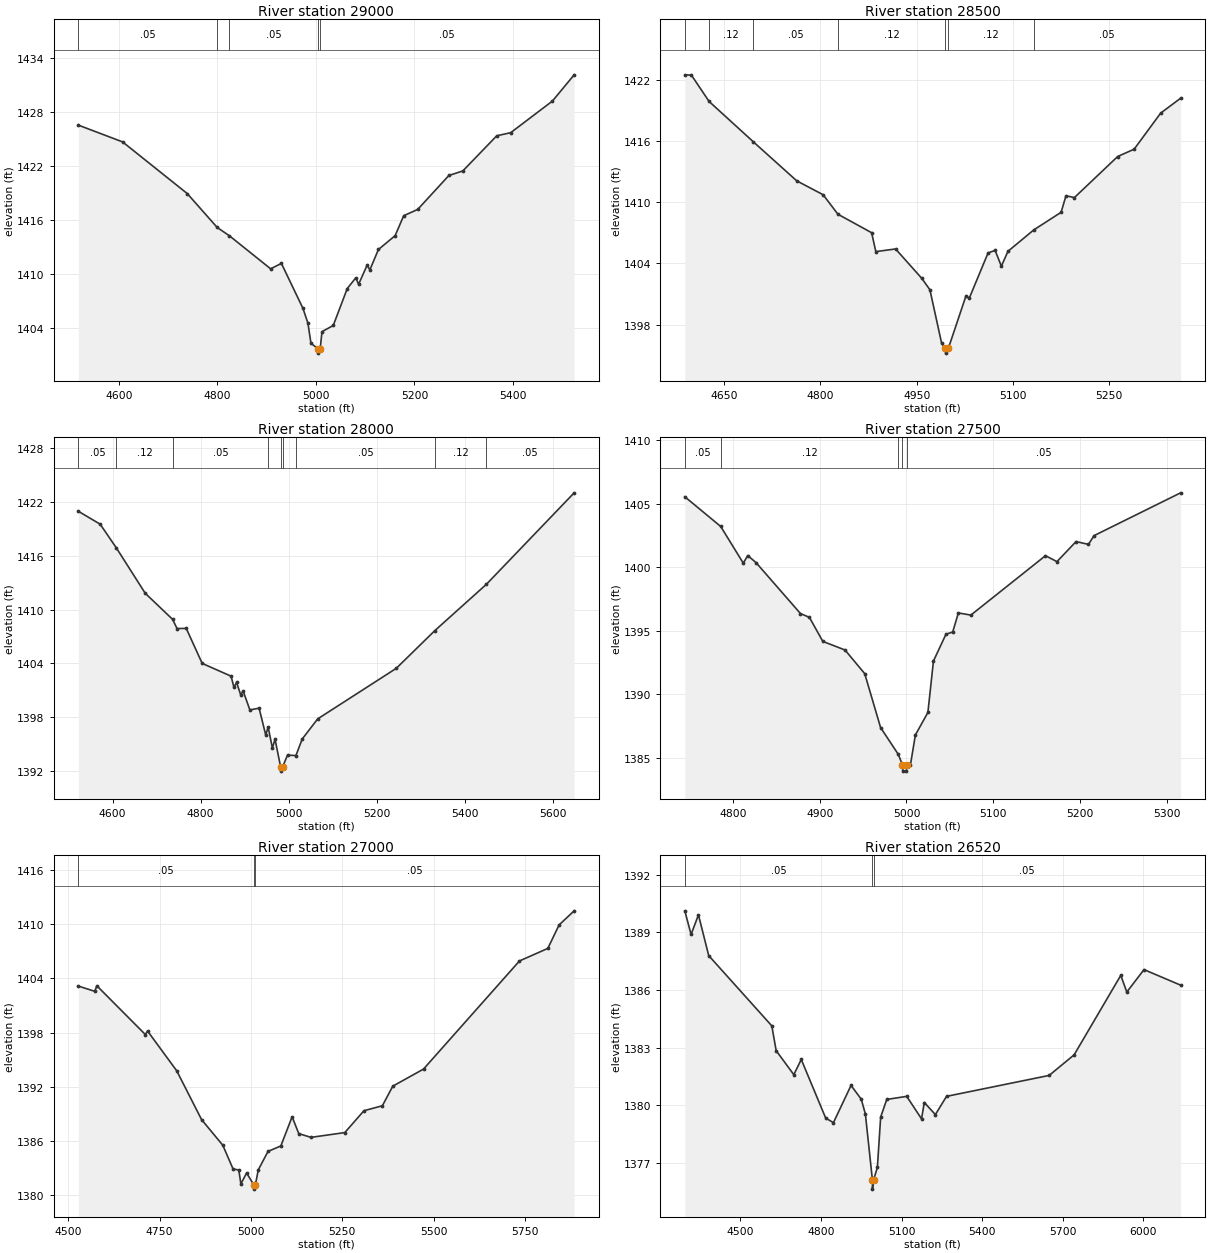
Type RM Length L Ch R = 1 ,29000   ,500,500,500
BEGIN DESCRIPTION:
SAND SPRING CREEK 57.0
END DESCRIPTION:
XS GIS Cut Line= 3
      2769355.65     10287303.09      2768931.31     10287073.44
      2768455.66      10286853.1
#Sta/Elev= 30
  4517.5 1426.56  4607.4 1424.69  4738.6 1418.94  4799.5 1415.16  4824.2 1414.24
  4907.9 1410.56  4929.8 1411.16  4973.6 1406.15  4983.7  1404.5  4989.8 1402.27
  5003.8 1401.67  5004.1 1401.17  5008.6 1401.67  5012.2 1403.56  5035.1 1404.25
  5063.5 1408.36  5080.9 1409.56  5086.5 1408.83  5103.9 1410.97  5109.4 1410.44
  5126.8 1412.71  5160.7 1414.25  5178.1 1416.47  5206.5 1417.17  5269.8 1420.95
  5298.2 1421.46    5367 1425.37  5395.4 1425.72  5480.1 1429.24  5524.2 1432.16
#Mann= 5 ,-1 , 0
  4517.5     .05       0  4799.5     .12       0  4824.2     .05       0
  5003.8     .05       0  5008.6     .05       0
Bank Sta=5003.8,5008.6
XS Rating Curve= 0 ,0
Exp/Cntr=0.3,0.1

Type RM Length L Ch R = 1 ,28500   ,500,500,500
BEGIN DESCRIPTION:
SAND SPRING CREEK 56.0
END DESCRIPTION:
XS GIS Cut Line= 3
      2769505.69     10286703.11      2769104.77     10286610.84
      2768755.66     10286703.12
#Sta/Elev= 30
  4588.6 1422.47  4598.9 1422.44  4626.5 1419.86  4695.4 1415.91    4763 1412.09
  4804.1 1410.73  4827.2 1408.82  4879.7 1407.01  4886.2 1405.16    4917 1405.42
    4958 1402.53  4970.5 1401.42  4988.8 1396.17  4994.5 1395.72  4994.9 1395.22
  4999.4 1395.72  5026.7 1400.83  5031.8  1400.6  5061.1 1405.03  5072.1 1405.28
  5081.8 1403.73  5092.1 1405.19  5132.2 1407.28  5174.9 1409.01  5182.5 1410.63
  5195.6 1410.45    5263 1414.47  5288.7 1415.19    5330 1418.72  5361.1 1420.18
#Mann= 7 ,-1 , 0
  4588.6     .05       0  4626.5     .12       0  4695.4     .05       0
  4827.2     .12       0  4994.5     .07       0  4999.4     .12       0
  5132.2     .05       0
Bank Sta=4994.5,4999.4
XS Rating Curve= 0 ,0
Exp/Cntr=0.3,0.1

Type RM Length L Ch R = 1 ,28000   ,500,500,500
BEGIN DESCRIPTION:
SAND SPRING CREEK 55.0
END DESCRIPTION:
XS GIS Cut Line= 3
      2769555.68     10286403.11       2769156.5       10286140.
      2768655.69      10286553.1
#Sta/Elev= 30
  4521.9 1420.93  4571.6 1419.49  4608.4 1416.85    4674 1411.81  4736.2 1408.91
  4746.3 1407.89  4767.3  1407.9  4803.5 1404.01  4869.2 1402.59  4875.7 1401.35
  4881.7 1401.89  4890.8 1400.55  4896.8 1400.91  4911.9 1398.84  4932.9 1399.03
    4948 1396.04  4953.4 1396.94  4963.1  1394.6  4969.1 1395.58  4981.7 1392.53
    4982 1392.03  4986.6 1392.53  4997.5 1393.81  5016.6 1393.76    5031 1395.61
  5066.1 1397.84  5244.7 1403.46  5332.3 1407.65  5449.7 1412.81  5649.2 1422.98
#Mann= 9 ,-1 , 0
  4521.9     .05       0  4608.4     .12       0  4736.2     .05       0
  4953.4     .12       0  4981.7     .07       0  4986.6     .12       0
  5016.6     .05       0  5332.3     .12       0  5449.7     .05       0
Bank Sta=4981.7,4986.6
XS Rating Curve= 0 ,0
Exp/Cntr=0.3,0.1

Type RM Length L Ch R = 1 ,27500   ,500,500,500
BEGIN DESCRIPTION:
SAND SPRING CREEK 54.0
END DESCRIPTION:
XS GIS Cut Line= 3
      2769055.72      10285753.1      2768806.58     10285809.33
      2768605.68     10286053.12
#Sta/Elev= 30
  4744.6 1405.54    4786  1403.2    4812 1400.31  4817.1 1400.91  4826.6 1400.36
  4877.9 1396.34  4888.2 1396.04  4903.6 1394.15  4929.2 1393.47  4951.9 1391.61
  4970.2 1387.36  4990.5 1385.26  4995.4 1384.43  4995.8 1383.93    5000 1383.93
  5000.4 1384.43  5004.6 1384.43  5010.3 1386.78  5024.7 1388.55  5031.1  1392.6
  5045.5 1394.71  5053.3 1394.89  5059.8 1396.39  5074.2 1396.22  5160.2  1400.9
  5173.4 1400.43  5195.4 1402.01  5209.7 1401.79  5216.2 1402.48  5315.9 1405.85
#Mann= 5 ,-1 , 0
  4744.6     .05       0    4786     .12       0  4990.5     .05       0
  4995.4     .05       0  5000.4     .05       0
Bank Sta=4995.4,5000.4
XS Rating Curve= 0 ,0
Exp/Cntr=0.3,0.1

Type RM Length L Ch R = 1 ,27000   ,480,480,480
BEGIN DESCRIPTION:
SAND SPRING CREEK 53.0
END DESCRIPTION:
XS GIS Cut Line= 3
      2769205.71     10285753.15      2768965.27     10285346.98
      2768105.64     10285553.12
#Sta/Elev= 30
    4528 1403.16  4572.9 1402.58  4578.7 1403.19  4711.4 1397.79  4717.2 1398.19
  4797.1 1393.78    4865 1388.38  4923.1 1385.54  4951.2 1382.91  4966.8  1382.8
  4972.6 1381.26  4988.2 1382.47  5007.4 1381.18  5007.8 1380.68  5012.4 1381.18
  5020.1 1382.81  5046.8 1384.86  5081.8 1385.46  5112.7 1388.69  5130.8 1386.83
  5164.1 1386.41  5256.7 1386.94  5309.1 1389.36  5359.5 1389.91    5388 1392.08
    5472 1393.97  5734.4 1405.94    5812 1407.33  5842.8 1409.93    5884 1411.49
#Mann= 3 ,-1 , 0
    4528     .05       0  5007.4     .03       0  5012.4     .05       0
Bank Sta=5007.4,5012.4
XS Rating Curve= 0 ,0
Exp/Cntr=0.3,0.1

Type RM Length L Ch R = 1 ,26520   ,440,440,440
BEGIN DESCRIPTION:
Mapping XS 591e4f66
END DESCRIPTION:
XS GIS Cut Line= 3
      2769683.96     10285684.65      2769321.84     10285014.73
      2768271.71     10284743.15
#Sta/Elev= 30
  4292.9 1390.12  4316.3 1388.89  4343.8 1389.91  4381.9 1387.79  4616.9 1384.13
  4633.1 1382.84  4698.8 1381.59  4726.6 1382.38  4817.5 1379.33  4846.3 1379.09
  4911.9 1381.03    4950 1380.31  4965.3 1379.54  4991.3 1376.13  4991.6 1375.63
  4996.3 1376.13    5010 1376.76  5022.2 1379.38  5044.9  1380.3  5119.2 1380.46
  5174.4 1379.29  5184.7 1380.14    5226 1379.51  5267.4 1380.46  5649.5 1381.55
  5742.5 1382.62  5916.3 1386.76  5938.7 1385.89  6002.7 1387.06  6139.1 1386.25
#Mann= 3 ,-1 , 0
  4292.9     .05       0  4991.3     .05       0  4996.3     .05       0
Bank Sta=4991.3,4996.3
XS Rating Curve= 0 ,0
Exp/Cntr=0.3,0.1