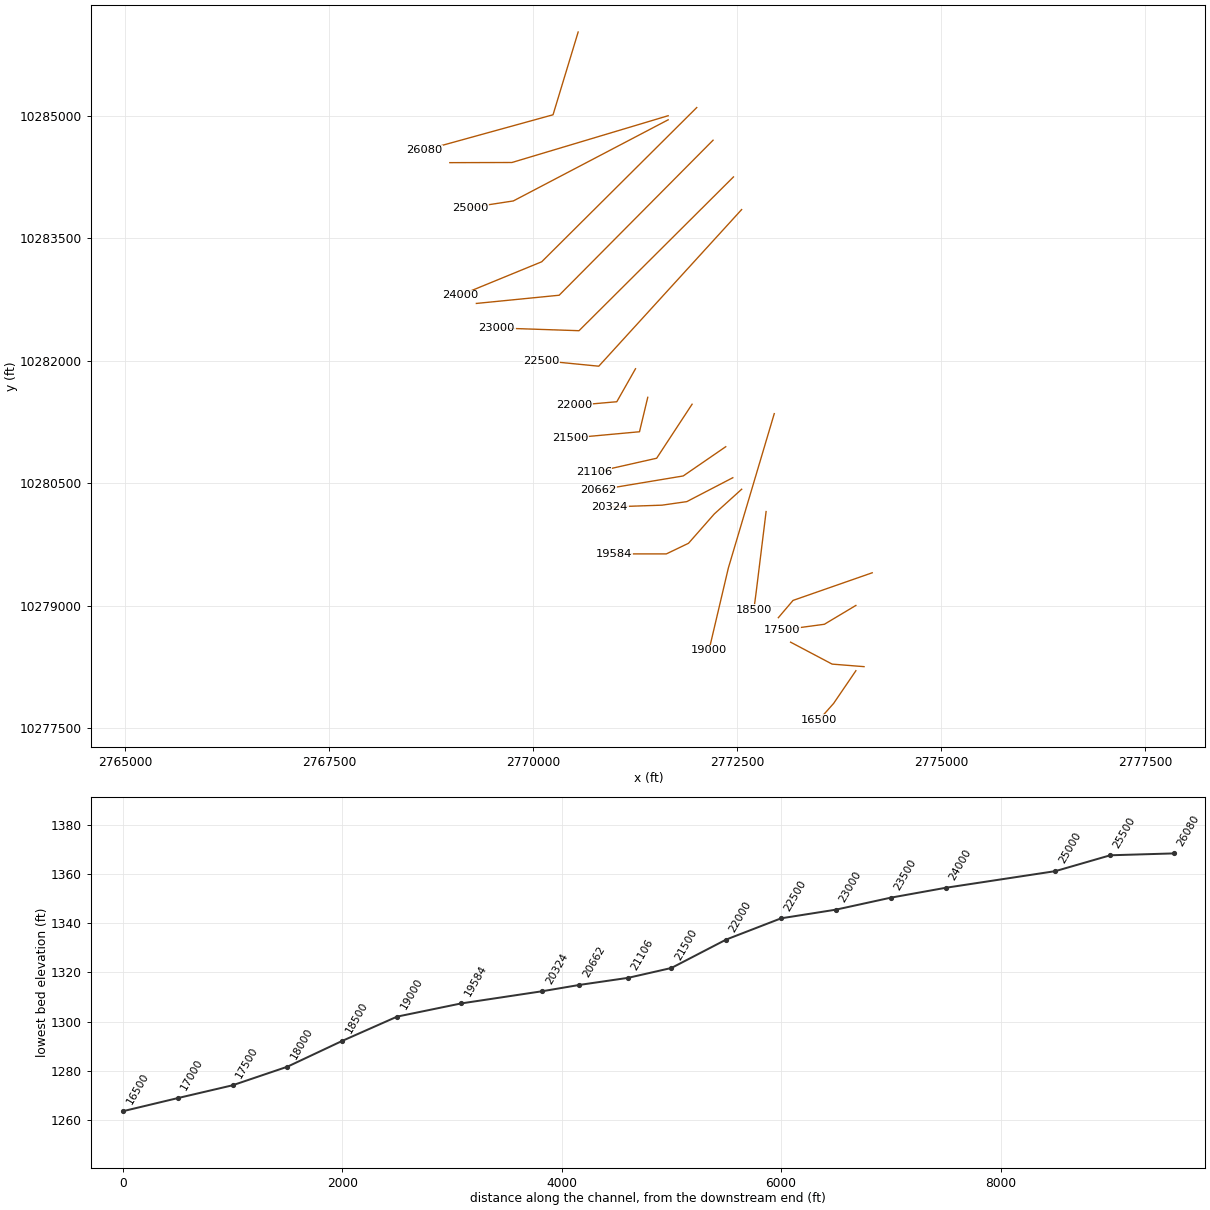
HEC-RAS study SAND SPRING CREEK.prj: SAND SPRING CREEK Base Level Engineering

--- SAND SPRING CREEK.g01 (geometry) --- (continued)

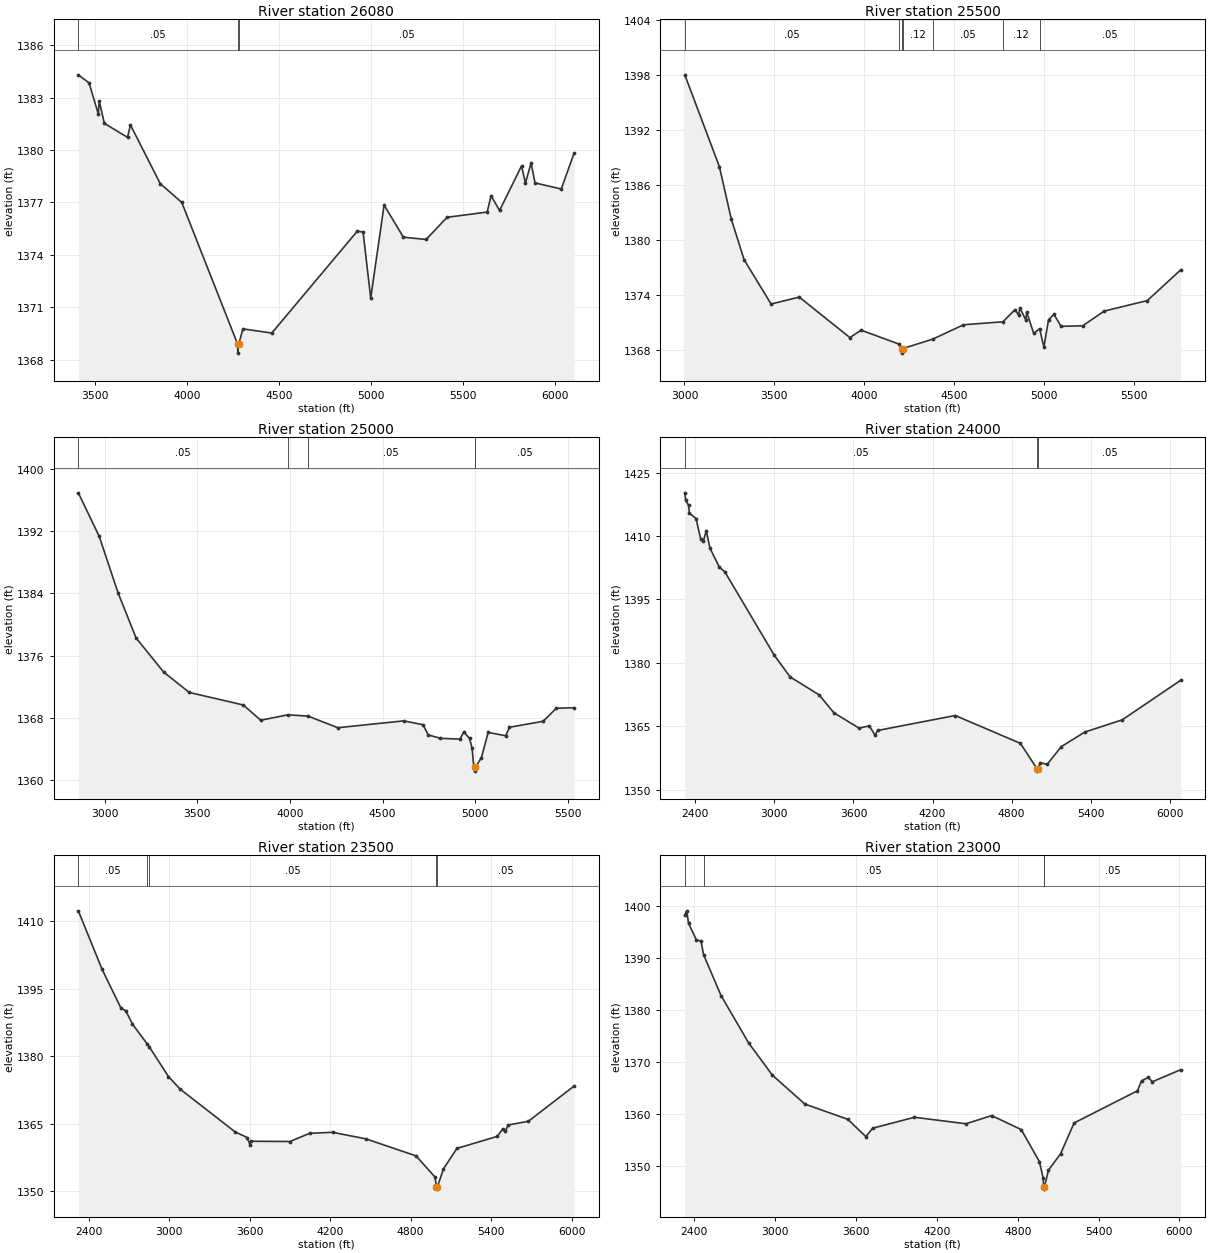
Type RM Length L Ch R = 1 ,26080   ,580,580,580
BEGIN DESCRIPTION:
Mapping XS 5da30611
END DESCRIPTION:
XS GIS Cut Line= 3
      2770553.06      10286028.7      2770245.25     10285014.73
      2768670.33     10284580.28
#Sta/Elev= 30
  3408.5 1384.31  3466.6 1383.85  3516.8 1382.08    3522 1382.81  3549.7 1381.53
  3675.6 1380.73  3691.7 1381.44  3853.3 1378.08  3970.5    1377  4274.4 1368.87
  4274.8 1368.37  4279.4 1368.87  4302.6 1369.76  4459.4 1369.52  4924.1 1375.36
  4955.3  1375.3  4996.8 1371.52  5069.4 1376.85  5174.1 1375.01  5297.6 1374.88
  5411.7 1376.15  5629.5 1376.45  5650.3 1377.39  5696.7 1376.54  5816.3  1379.1
    5837 1378.11  5868.1 1379.27  5889.2 1378.12  6031.9 1377.77  6101.9 1379.84
#Mann= 3 ,-1 , 0
  3408.5     .05       0  4274.4     .05       0  4279.4     .05       0
Bank Sta=4274.4,4279.4
XS Rating Curve= 0 ,0
Exp/Cntr=0.3,0.1

Type RM Length L Ch R = 1 ,25500   ,500,500,500
BEGIN DESCRIPTION:
SAND SPRING CREEK 50.0
END DESCRIPTION:
XS GIS Cut Line= 3
      2771655.69     10285003.11      2769741.36     10284429.95
      2768980.66     10284428.11
#Sta/Elev= 30
  3001.7 1398.05  3194.1 1388.01  3260.3 1382.28  3331.7 1377.83  3481.9 1372.98
  3638.5 1373.74  3920.3 1369.31  3982.9 1370.12  4193.5  1368.6  4210.1 1368.11
  4210.4 1367.61  4215.1 1368.11  4382.5 1369.15  4552.5 1370.71  4772.3 1371.04
  4838.9 1372.36  4859.8 1371.76    4866 1372.57  4899.1 1371.24  4904.3 1372.09
  4943.3 1369.76  4975.9 1370.29    5000 1368.28  5025.7 1371.26  5055.7 1371.85
  5095.7 1370.54  5215.7  1370.6  5335.7 1372.21  5575.7 1373.36  5760.7 1376.71
#Mann= 7 ,-1 , 0
  3001.7     .05       0  4193.5     .12       0  4210.1     .05       0
  4215.1     .12       0  4382.5     .05       0  4772.3     .12       0
  4975.9     .05       0
Bank Sta=4210.1,4215.1
XS Rating Curve= 0 ,0
Exp/Cntr=0.3,0.1

Type RM Length L Ch R = 1 ,25000   ,1000,1000,1000
BEGIN DESCRIPTION:
SAND SPRING CREEK 49.0
END DESCRIPTION:
XS GIS Cut Line= 3
      2771655.72     10284953.13      2769758.75     10283958.95
      2769230.71     10283878.11
#Sta/Elev= 30
  2858.3 1396.89  2971.2 1391.29  3072.9 1384.04  3169.8 1378.27  3318.5 1373.89
  3456.7 1371.27  3748.5 1369.66  3842.4  1367.7  3989.4  1368.4  4098.4 1368.23
  4258.3 1366.74    4614 1367.62  4718.7 1367.13  4746.4 1365.82  4812.6 1365.38
  4917.2 1365.28  4939.3 1366.19  4969.6 1365.36  4983.4 1364.12  4992.2 1361.79
  4996.4 1361.67  4996.8 1361.17  5001.5 1361.67  5033.5 1362.89  5070.2 1366.14
    5165 1365.71  5185.2  1366.8  5367.3 1367.57  5438.1 1369.24  5534.2 1369.31
#Mann= 5 ,-1 , 0
  2858.3     .05       0  3989.4     .12       0  4098.4     .05       0
  4996.4     .05       0  5001.5     .05       0
Bank Sta=4996.4,5001.5
XS Rating Curve= 0 ,0
Exp/Cntr=0.3,0.1

Type RM Length L Ch R = 1 ,24000   ,500,500,500
BEGIN DESCRIPTION:
SAND SPRING CREEK 47.0
END DESCRIPTION:
XS GIS Cut Line= 3
      2772005.72     10285103.15      2770106.47     10283213.59
      2769105.68     10282803.11
#Sta/Elev= 30
  2320.9  1420.2    2328 1418.39  2349.2  1417.3  2356.3 1415.38  2405.8 1414.13
  2441.2 1409.33  2462.4 1408.85  2483.6 1411.25  2511.9 1407.11  2582.6 1402.66
    2625  1401.5  2999.8 1381.79    3120 1376.67  3339.2 1372.44  3452.3 1368.18
  3643.3 1364.56    3721 1365.12  3763.4 1362.91  3784.7 1364.02  4371.6 1367.55
  4866.5 1360.97  4993.7  1354.9  4994.2  1354.4  5000.4  1354.9  5015.7 1356.42
  5069.1 1355.98  5175.9 1360.18  5354.6 1363.63  5638.5 1366.52  6081.7 1375.87
#Mann= 3 ,-1 , 0
  2320.9     .05       0  4993.7     .03       0  5000.4     .05       0
Bank Sta=4993.7,5000.4
XS Rating Curve= 0 ,0
Exp/Cntr=0.3,0.1

Type RM Length L Ch R = 1 ,23500   ,500,500,500
BEGIN DESCRIPTION:
SAND SPRING CREEK 46.0
END DESCRIPTION:
XS GIS Cut Line= 3
      2772205.71     10284703.14      2770320.15     10282803.72
      2769305.73     10282703.12
#Sta/Elev= 30
  2323.6 1412.35  2500.4 1399.34  2641.8 1390.66  2677.2 1390.12  2726.7 1387.14
  2838.1 1382.67  2851.7 1382.11  2995.4 1375.46  3080.3 1372.71  3490.4 1363.17
  3582.3 1361.87  3603.5 1360.26  3610.6 1361.05  3900.5 1360.99    4049 1362.82
  4218.7 1363.04  4466.2 1361.59    4841 1357.79  4982.4 1353.07  4993.1 1350.89
  4993.6 1350.39  4999.9 1350.89  5044.7 1354.86  5145.2 1359.45  5446.7 1362.14
  5486.8 1363.81  5506.9 1363.24    5527 1364.66  5677.8 1365.49  6019.4 1373.35
#Mann= 5 ,-1 , 0
  2323.6     .05       0  2838.1     .12       0  2851.7     .05       0
  4993.1     .05       0  4999.9     .05       0
Bank Sta=4993.1,4999.9
XS Rating Curve= 0 ,0
Exp/Cntr=0.3,0.1

Type RM Length L Ch R = 1 ,23000   ,500,500,500
BEGIN DESCRIPTION:
SAND SPRING CREEK 45.0
END DESCRIPTION:
XS GIS Cut Line= 3
      2772455.69     10284253.12      2770563.54     10282369.19
      2769555.71     10282403.11
#Sta/Elev= 30
  2329.9 1398.36    2344 1399.12  2358.2 1396.69  2414.7 1393.58  2450.1 1393.22
  2469.7 1390.65  2598.6 1382.81  2803.7 1373.67  2980.4 1367.45  3220.9  1361.9
  3539.1 1358.97  3673.4 1355.63  3722.9 1357.25    4034 1359.36  4415.9 1358.11
  4606.8 1359.68    4826 1356.99  4960.4 1350.83  4988.6 1347.68  4991.6 1346.02
  4992.1 1345.52  4998.4 1346.02  5027.9 1349.16  5117.9 1352.33    5218 1358.26
  5688.2 1364.46  5718.3 1366.38  5768.3 1367.03  5798.3  1366.2  6008.4 1368.51
#Mann= 4 ,-1 , 0
  2329.9     .12       0  2469.7     .05       0  4991.6     .03       0
  4998.4     .05       0
Bank Sta=4991.6,4998.4
XS Rating Curve= 0 ,0
Exp/Cntr=0.3,0.1

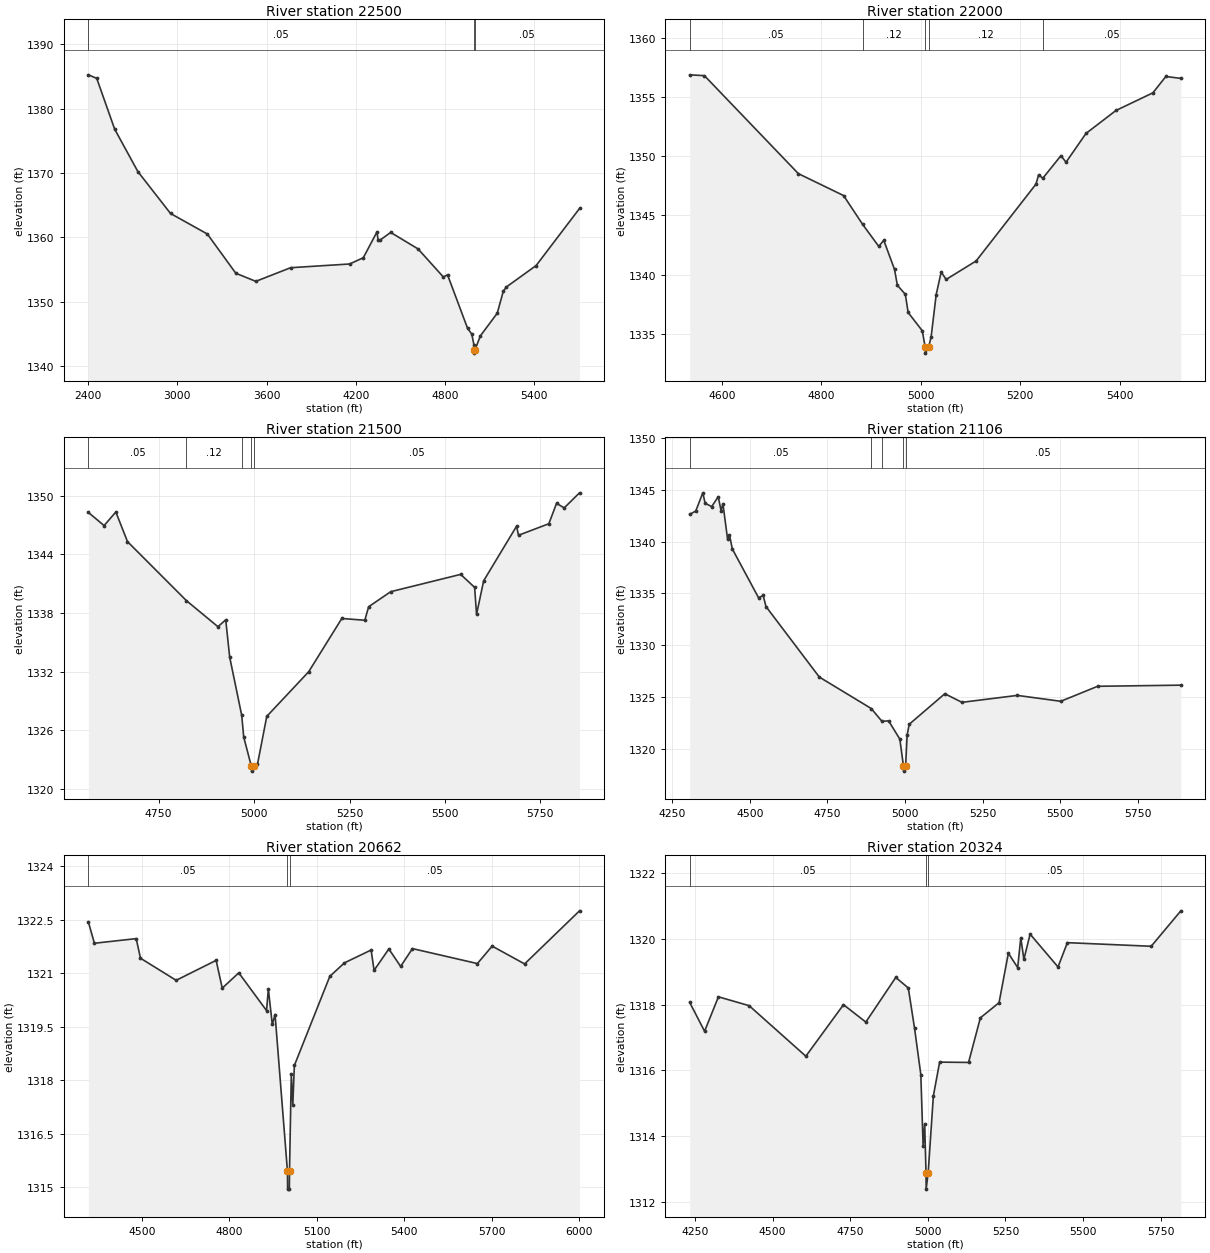
Type RM Length L Ch R = 1 ,22500   ,500,500,500
BEGIN DESCRIPTION:
SAND SPRING CREEK 44.0
END DESCRIPTION:
XS GIS Cut Line= 3
      2772555.67      10283853.1      2770805.57     10281934.23
      2770105.65     10282003.11
#Sta/Elev= 30
  2402.9 1385.27  2459.3 1384.72  2579.6 1376.83  2735.6 1370.23  2955.2 1363.71
  3202.5 1360.52  3393.7 1354.42  3528.2 1353.16  3761.9 1355.28  4158.5 1355.86
  4250.4 1356.83  4342.3 1360.84  4349.7 1359.63  4363.9 1359.58  4434.2 1360.77
  4618.6  1358.2  4788.2 1353.84  4816.6 1354.17    4951 1345.86  4979.4 1344.96
  4993.6 1343.32  4993.9  1342.5  4994.4    1342  5000.8  1342.5  5037.3 1344.69
  5150.6 1348.21  5190.8  1351.6  5210.9 1352.27  5411.9 1355.62  5703.3 1364.49
#Mann= 3 ,-1 , 0
  2402.9     .05       0  4993.9     .03       0  5000.8     .05       0
Bank Sta=4993.9,5000.8
XS Rating Curve= 0 ,0
Exp/Cntr=0.3,0.1

Type RM Length L Ch R = 1 ,22000   ,500,500,500
BEGIN DESCRIPTION:
SAND SPRING CREEK 43.0
END DESCRIPTION:
XS GIS Cut Line= 3
      2771255.67     10281903.09      2771026.44     10281498.87
      2770505.65     10281453.11
#Sta/Elev= 30
  4535.3 1356.87  4564.9  1356.8  4753.8 1348.53  4844.7 1346.68  4882.8 1344.26
  4915.4 1342.39  4925.5  1342.9  4947.1 1340.45  4952.9  1339.1  4968.8 1338.35
  4974.5 1336.81  5002.9 1335.27  5008.8 1333.88  5009.3 1333.38  5015.7 1333.88
  5020.8 1334.78  5030.9 1338.32  5040.9 1340.22    5051  1339.6  5111.2 1341.16
  5231.6 1347.65  5236.9 1348.44  5245.2 1348.14  5281.8 1350.05  5291.9 1349.49
    5332 1351.92  5392.3 1353.86  5466.6 1355.35  5492.6 1356.73  5522.8 1356.57
#Mann= 5 ,-1 , 0
  4535.3     .05       0  4882.8     .12       0  5008.8     .07       0
  5015.7     .12       0  5245.2     .05       0
Bank Sta=5008.8,5015.7
XS Rating Curve= 0 ,0
Exp/Cntr=0.3,0.1

Type RM Length L Ch R = 1 ,21500   ,394,394,394
BEGIN DESCRIPTION:
SAND SPRING CREEK 42.0
END DESCRIPTION:
XS GIS Cut Line= 3
      2771405.69     10281553.14      2771304.54     10281131.09
      2770455.72     10281053.11
#Sta/Elev= 30
    4566 1348.28  4607.2 1346.93    4638 1348.32  4668.5 1345.29    4823 1339.25
  4905.4 1336.59  4925.8 1337.29  4936.2 1333.47  4967.7 1327.52  4972.9 1325.31
  4992.9 1322.32  4993.4 1321.82  4999.9 1322.32  5008.9 1322.51  5033.3 1327.42
  5143.2 1331.99  5229.8 1337.43  5290.1 1337.25  5300.1 1338.63  5357.9 1340.17
  5541.1 1341.94  5577.7 1340.61  5582.7 1337.85  5601.4 1341.29  5687.6 1346.87
  5692.6 1345.94  5772.1 1347.12  5792.2  1349.2  5812.3 1348.74  5852.4 1350.28
#Mann= 5 ,-1 , 0
    4566     .05       0    4823     .12       0  4967.7     .05       0
  4992.9     .03       0  4999.9     .05       0
Bank Sta=4992.9,4999.9
XS Rating Curve= 0 ,0
Exp/Cntr=0.3,0.1

Type RM Length L Ch R = 1 ,21106   ,444,444,444
BEGIN DESCRIPTION:
Mapping XS b8a79aa6
END DESCRIPTION:
XS GIS Cut Line= 3
      2771948.73      10281468.5      2771514.68     10280806.57
      2770744.25     10280632.96
#Sta/Elev= 30
  4306.5 1342.64    4326 1342.96  4348.8 1344.72  4356.2 1343.71  4377.3 1343.39
  4398.4 1344.34  4407.5    1343  4413.5 1343.66  4428.6 1340.22  4434.6 1340.65
  4443.7  1339.3  4528.2 1334.58  4543.1  1334.8  4552.1 1333.73  4723.9 1326.91
  4891.1 1323.87  4925.5 1322.63    4947 1322.68  4983.1 1320.91  4994.7 1318.32
  4995.2 1317.82  5001.7 1318.32  5006.5 1321.29  5013.3 1322.35  5127.8  1325.3
  5183.1 1324.47  5361.2 1325.14  5501.2 1324.57  5619.8 1326.02  5887.8 1326.13
#Mann= 5 ,-1 , 0
  4306.5     .05       0  4891.1     .12       0  4925.5     .05       0
  4994.7     .03       0  5001.7     .05       0
Bank Sta=4994.7,5001.7
XS Rating Curve= 0 ,0
Exp/Cntr=0.3,0.1

Type RM Length L Ch R = 1 ,20662   ,338,338,338
BEGIN DESCRIPTION:
Mapping XS ac7695dd
END DESCRIPTION:
XS GIS Cut Line= 3
      2772361.07     10280947.66       2771840.2     10280589.56
      2770799.65     10280416.14
#Sta/Elev= 30
  4315.2 1322.44    4336 1321.84  4479.5 1321.97  4494.3 1321.42  4616.8  1320.8
  4754.1 1321.36  4775.1 1320.58  4831.9 1321.01  4927.3 1319.95  4933.4 1320.56
    4947 1319.56  4956.5 1319.84  4999.1 1315.44  4999.6 1314.94  5005.6 1314.94
  5006.1 1315.44  5012.3 1318.17  5017.4  1317.3  5022.8 1318.41  5144.5 1320.91
  5194.8 1321.29  5286.4 1321.65  5296.6 1321.08  5347.3 1321.68  5387.8 1321.19
  5428.4 1321.69  5651.4 1321.27  5702.1 1321.76  5813.6 1321.26  6002.2 1322.75
#Mann= 3 ,-1 , 0
  4315.2     .05       0  4999.1     .05       0  5006.1     .05       0
Bank Sta=4999.1,5006.1
XS Rating Curve= 0 ,0
Exp/Cntr=0.3,0.1

Type RM Length L Ch R = 1 ,20324   ,740,740,740
BEGIN DESCRIPTION:
Mapping XS ebe2b85b
END DESCRIPTION:
XS GIS Cut Line= 4
      2772447.88     10280567.88       2771883.6     10280274.89
      2771579.79     10280231.49      2770940.16     10280209.81
#Sta/Elev= 30
  4232.6 1318.07  4280.6 1317.19  4325.2 1318.24  4424.2 1317.97  4606.9 1316.43
  4728.2    1318  4800.2 1317.47  4896.6 1318.83    4937 1318.51  4957.2 1317.28
  4977.4 1315.87  4984.8 1313.69  4989.8 1314.37  4994.1 1312.88  4994.6 1312.38
  5001.1 1312.88  5017.8 1315.22    5038 1316.25  5131.2 1316.24  5169.3  1317.6
  5229.4 1318.06  5259.5 1319.57  5289.5 1319.13  5299.5 1320.04  5309.5 1319.38
  5329.5 1320.15  5419.5 1319.15  5449.6 1319.89  5719.7 1319.78  5815.3 1320.86
#Mann= 3 ,-1 , 0
  4232.6     .05       0  4994.1     .05       0  5001.1     .05       0
Bank Sta=4994.1,5001.1
XS Rating Curve= 0 ,0
Exp/Cntr=0.3,0.1

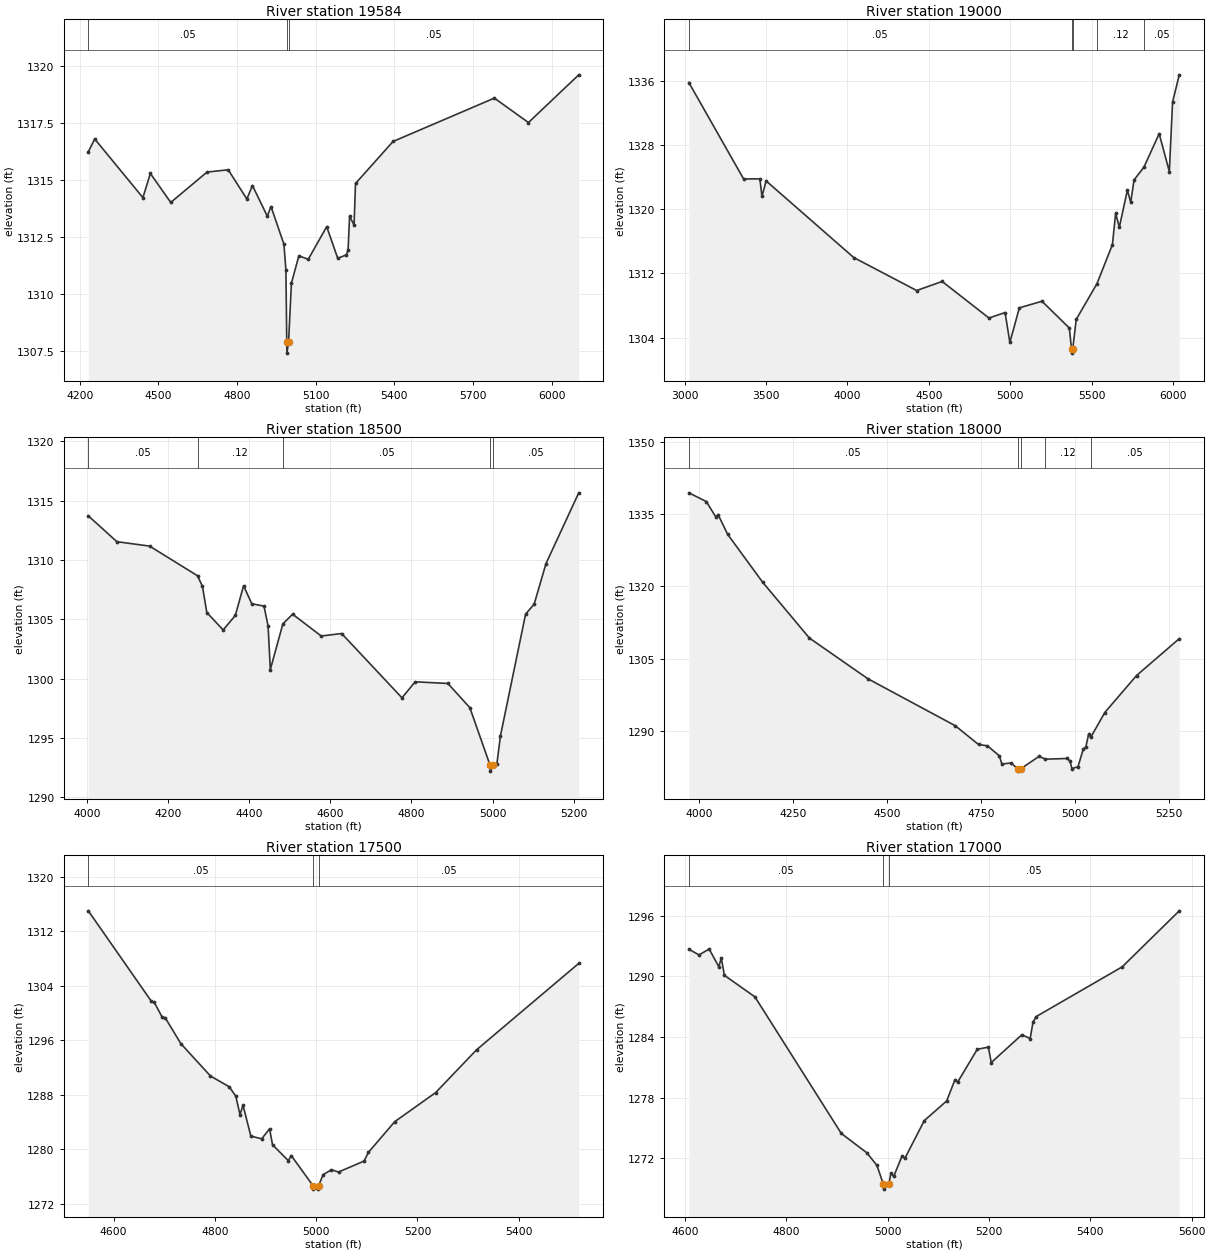
Type RM Length L Ch R = 1 ,19584   ,584,584,584
BEGIN DESCRIPTION:
Mapping XS 489732ee
END DESCRIPTION:
XS GIS Cut Line= 5
      2772556.35      10280426.8      2772219.98     10280122.98
      2771905.31     10279764.91      2771634.04      10279634.7
       2770993.8      10279634.7
#Sta/Elev= 30
  4232.8 1316.24  4257.3  1316.8  4441.1 1314.23  4469.5 1315.29  4547.3 1314.02
  4685.6 1315.35  4766.6 1315.45  4837.7 1314.17    4859 1314.76  4915.6 1313.42
  4929.8 1313.84  4979.1 1312.19  4986.7 1311.06  4989.9 1307.92  4990.4 1307.42
  4996.9 1307.92  5007.6 1310.48  5036.1 1311.68    5072 1311.53  5142.3 1312.96
  5184.5 1311.57  5217.8 1311.73    5224 1311.95  5229.6 1313.42  5246.7 1313.03
  5252.2 1314.85  5395.3 1316.69    5782 1318.59    5912 1317.52  6103.9 1319.61
#Mann= 3 ,-1 , 0
  4232.8     .05       0  4989.9     .05       0  4996.9     .05       0
Bank Sta=4989.9,4996.9
XS Rating Curve= 0 ,0
Exp/Cntr=0.3,0.1

Type RM Length L Ch R = 1 ,19000   ,500,500,500
BEGIN DESCRIPTION:
SAND SPRING CREEK 38.0
END DESCRIPTION:
XS GIS Cut Line= 3
       2772955.7     10281353.15      2772393.14     10279461.63
      2772155.68     10278453.11
#Sta/Elev= 30
  3026.6 1335.81  3362.8 1323.78  3462.4  1323.8  3475.3  1321.6  3500.8 1323.54
  4038.6 1313.98  4424.6 1309.87  4581.1    1311  4868.2 1306.44  4967.2 1307.12
  4996.6 1303.39  5054.7 1307.71  5193.7 1308.53  5361.5 1305.19  5374.9 1302.56
  5375.4 1302.06  5382.3 1302.56  5403.8 1306.27  5531.2 1310.73  5625.9  1315.6
  5645.7 1319.51  5668.3 1317.76  5717.6 1322.38  5738.2 1320.88  5758.7 1323.66
  5819.4 1325.26  5912.8 1329.43  5975.1  1324.7    5995 1333.38  6036.1 1336.77
#Mann= 5 ,-1 , 0
  3026.6     .05       0  5374.9     .05       0  5382.3     .05       0
  5531.2     .12       0  5819.4     .05       0
Bank Sta=5374.9,5382.3
XS Rating Curve= 0 ,0
Exp/Cntr=0.3,0.1

Type RM Length L Ch R = 1 ,18500   ,500,500,500
BEGIN DESCRIPTION:
SAND SPRING CREEK 37.0
END DESCRIPTION:
XS GIS Cut Line= 3
      2772855.68     10280153.07      2772733.69     10279163.86
      2772705.68     10278953.11
#Sta/Elev= 30
  4003.3 1313.72  4073.8 1311.54  4154.4 1311.17  4272.6 1308.67  4284.8 1307.77
  4295.5 1305.57  4335.8  1304.1  4365.9 1305.33  4386.1 1307.83  4406.3 1306.31
  4436.5 1306.11  4446.6 1304.44  4452.1 1300.76    4483 1304.61    4507 1305.43
  4577.6 1303.59    4628  1303.8  4776.7 1298.38  4809.3 1299.73  4889.9 1299.59
  4944.1 1297.55  4993.9  1292.7  4994.4  1292.2  5001.9  1292.7  5010.8 1292.82
  5019.4 1295.15  5081.5 1305.43  5102.7 1306.28  5131.9  1309.7  5212.6 1315.66
#Mann= 5 ,-1 , 0
  4003.3     .05       0  4272.6     .12       0    4483     .05       0
  4993.9     .05       0  5001.9     .05       0
Bank Sta=4993.9,5001.9
XS Rating Curve= 0 ,0
Exp/Cntr=0.3,0.1

Type RM Length L Ch R = 1 ,18000   ,500,500,500
BEGIN DESCRIPTION:
SAND SPRING CREEK 36.0
END DESCRIPTION:
XS GIS Cut Line= 3
       2774155.7     10279403.12      2773185.76     10279064.63
      2773005.68      10278853.1
#Sta/Elev= 30
  3972.7  1339.4  4019.3 1337.59  4045.1 1334.31  4050.4  1334.9  4076.1 1330.78
  4169.3 1320.85  4293.6 1309.29  4449.3 1300.85  4681.5 1291.13  4743.6 1287.23
  4767.1 1286.96  4798.8  1284.9  4805.7 1283.19  4830.6  1283.4  4847.3 1282.21
  4847.8 1281.71  4856.3 1282.21  4904.8 1284.78  4921.6 1284.19  4978.9 1284.33
  4986.8 1283.84  4992.1 1282.24  5008.2 1282.61  5022.5 1286.32    5029 1286.69
  5036.8 1289.44  5042.1  1288.7  5079.6 1293.86  5164.1 1301.53  5277.8 1309.17
#Mann= 5 ,-1 , 0
  3972.7     .05       0  4847.3     .07       0  4856.3     .05       0
  4921.6     .12       0  5042.1     .05       0
Bank Sta=4847.3,4856.3
XS Rating Curve= 0 ,0
Exp/Cntr=0.3,0.1

Type RM Length L Ch R = 1 ,17500   ,500,500,500
BEGIN DESCRIPTION:
SAND SPRING CREEK 35.0
END DESCRIPTION:
XS GIS Cut Line= 3
      2773955.64     10279003.09      2773569.56      10278772.3
       2773055.7     10278703.11
#Sta/Elev= 30
  4550.2 1314.98  4674.7 1301.71  4680.5 1301.55  4696.1 1299.37  4701.9 1299.31
    4733 1295.49  4791.4 1290.75  4828.3 1289.18  4841.4  1287.8  4849.7 1285.06
  4855.6 1286.48  4871.1 1281.94  4892.5 1281.54  4908.1 1283.01  4913.9 1280.66
  4945.1 1278.34  4950.9 1279.08  4993.9 1274.66  4994.4 1274.16  5004.3 1274.16
  5004.8 1274.66    5014  1276.3  5030.3    1277  5044.3 1276.67  5094.7 1278.28
  5103.1 1279.54  5155.3 1284.06    5236 1288.32  5316.7 1294.59  5518.5 1307.27
#Mann= 3 ,-1 , 0
  4550.2     .05       0  4993.9     .05       0  5004.8     .05       0
Bank Sta=4993.9,5004.8
XS Rating Curve= 0 ,0
Exp/Cntr=0.3,0.1

Type RM Length L Ch R = 1 ,17000   ,500,500,500
BEGIN DESCRIPTION:
SAND SPRING CREEK 34.0
END DESCRIPTION:
XS GIS Cut Line= 3
      2774055.68     10278253.11      2773664.62      10278284.2
      2773155.69     10278553.11
#Sta/Elev= 30
  4607.7 1292.68  4627.8 1292.12  4647.8  1292.7  4666.8 1290.96  4671.8 1291.81
  4677.9  1290.1  4738.1 1287.97  4908.6 1274.46  4958.8 1272.55  4978.9  1271.3
  4991.5 1269.45    4992 1268.95  5002.5 1269.45  5006.4  1270.5  5012.1 1270.22
  5028.4 1272.22  5034.1    1272  5072.4 1275.73  5116.5 1277.67  5132.8 1279.76
  5138.5 1279.56  5176.9 1282.78  5198.9    1283  5204.5 1281.47  5264.9 1284.22
  5281.3 1283.85  5286.9 1285.46  5292.9 1286.01    5463 1290.94  5575.6 1296.48
#Mann= 3 ,-1 , 0
  4607.7     .05       0  4991.5     .05       0  5002.5     .05       0
Bank Sta=4991.5,5002.5
XS Rating Curve= 0 ,0
Exp/Cntr=0.3,0.1

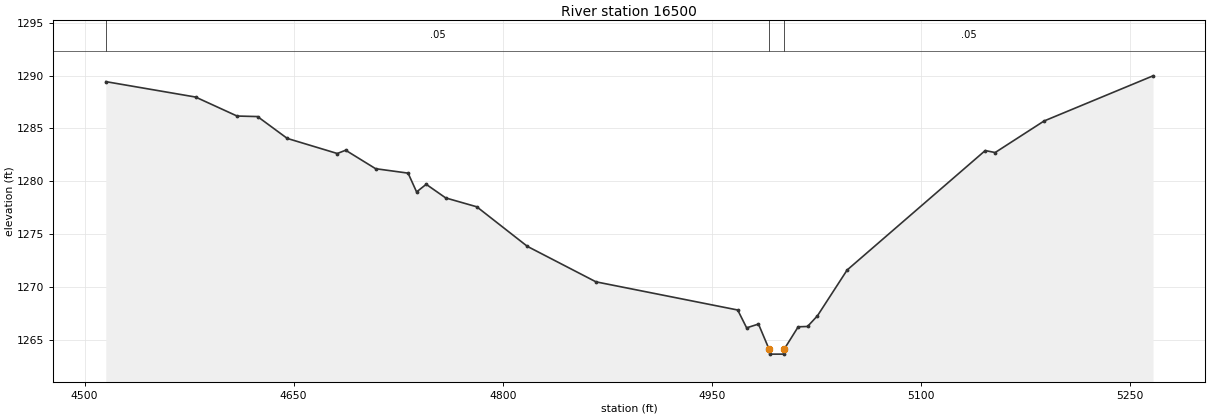
Type RM Length L Ch R = 1 ,16500   ,500,500,500
BEGIN DESCRIPTION:
SAND SPRING CREEK 33.0
END DESCRIPTION:
XS GIS Cut Line= 3
      2773955.69     10278203.12      2773682.78     10277802.43
      2773505.71     10277603.14
#Sta/Elev= 30
  4515.2 1289.44  4579.6 1287.98  4609.4 1286.18  4624.1 1286.13  4645.4 1284.06
  4681.3 1282.63  4687.3 1282.94  4708.8 1281.19  4732.1 1280.77  4738.2 1278.99
  4745.1 1279.71  4759.1 1278.42  4781.4 1277.58  4817.7 1273.83  4866.9 1270.47
  4968.6  1267.8    4975 1266.11  4983.5 1266.47    4991 1264.12  4991.5 1263.62
  5001.6 1263.62  5002.1 1264.12    5012 1266.21  5018.7 1266.24  5025.8 1267.25
  5047.1 1271.59  5146.2 1282.91  5153.3 1282.72  5188.4 1285.71  5266.6 1289.99
#Mann= 3 ,-1 , 0
  4515.2     .05       0    4991     .05       0  5002.1     .05       0
Bank Sta=4991,5002.1
XS Rating Curve= 0 ,0
Exp/Cntr=0.3,0.1