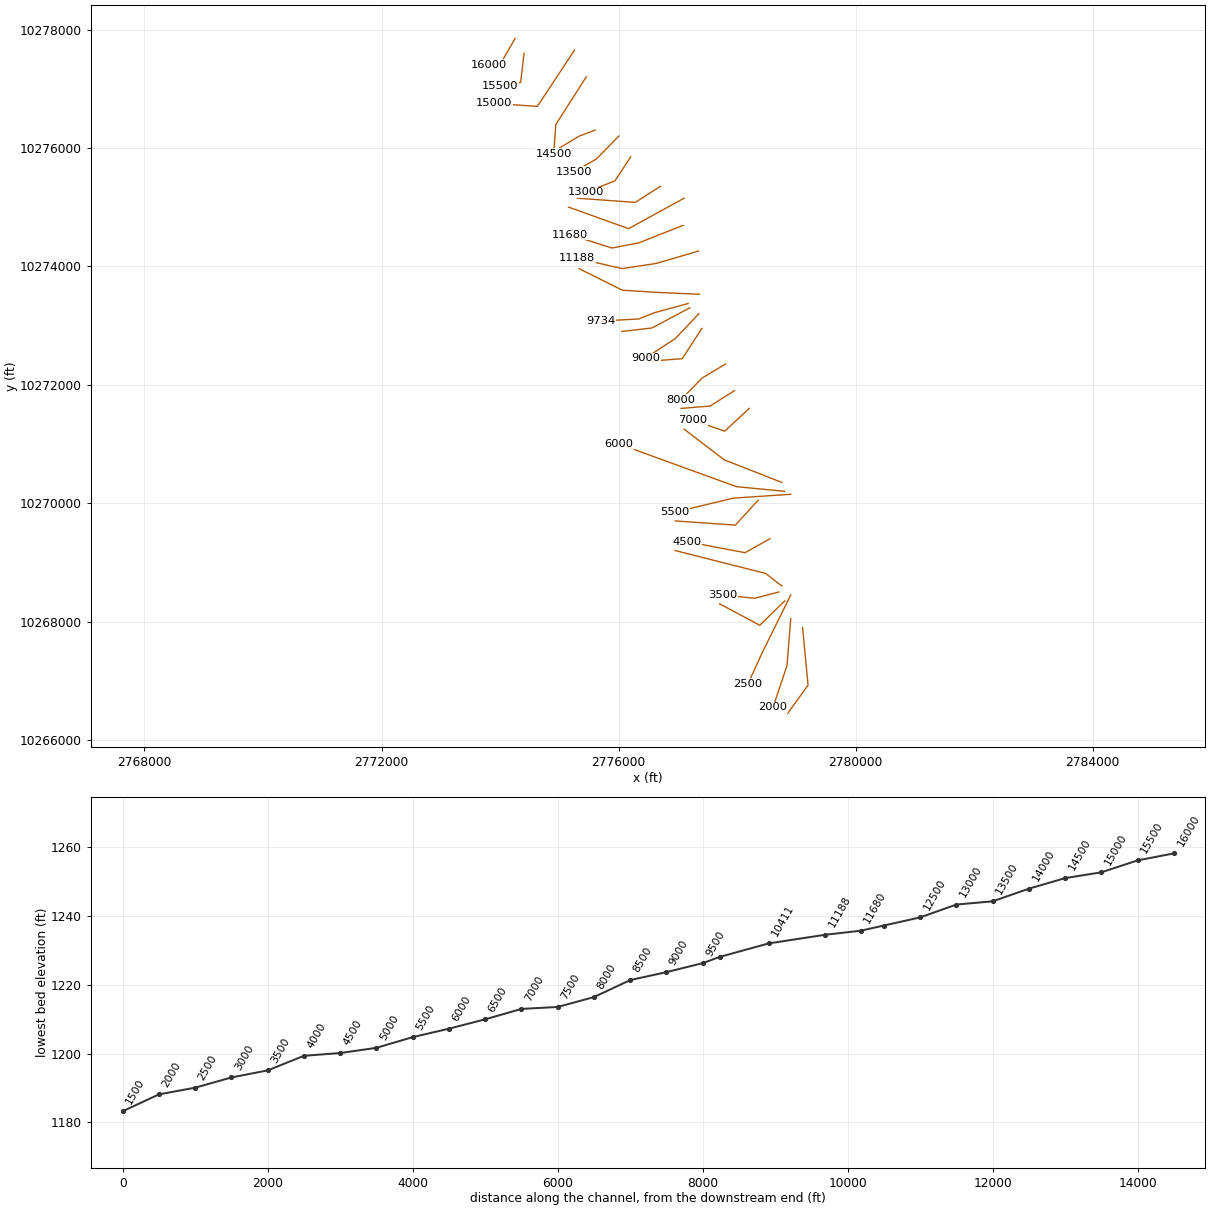
HEC-RAS study SAND SPRING CREEK.prj: SAND SPRING CREEK Base Level Engineering

--- SAND SPRING CREEK.g01 (geometry) --- (continued)

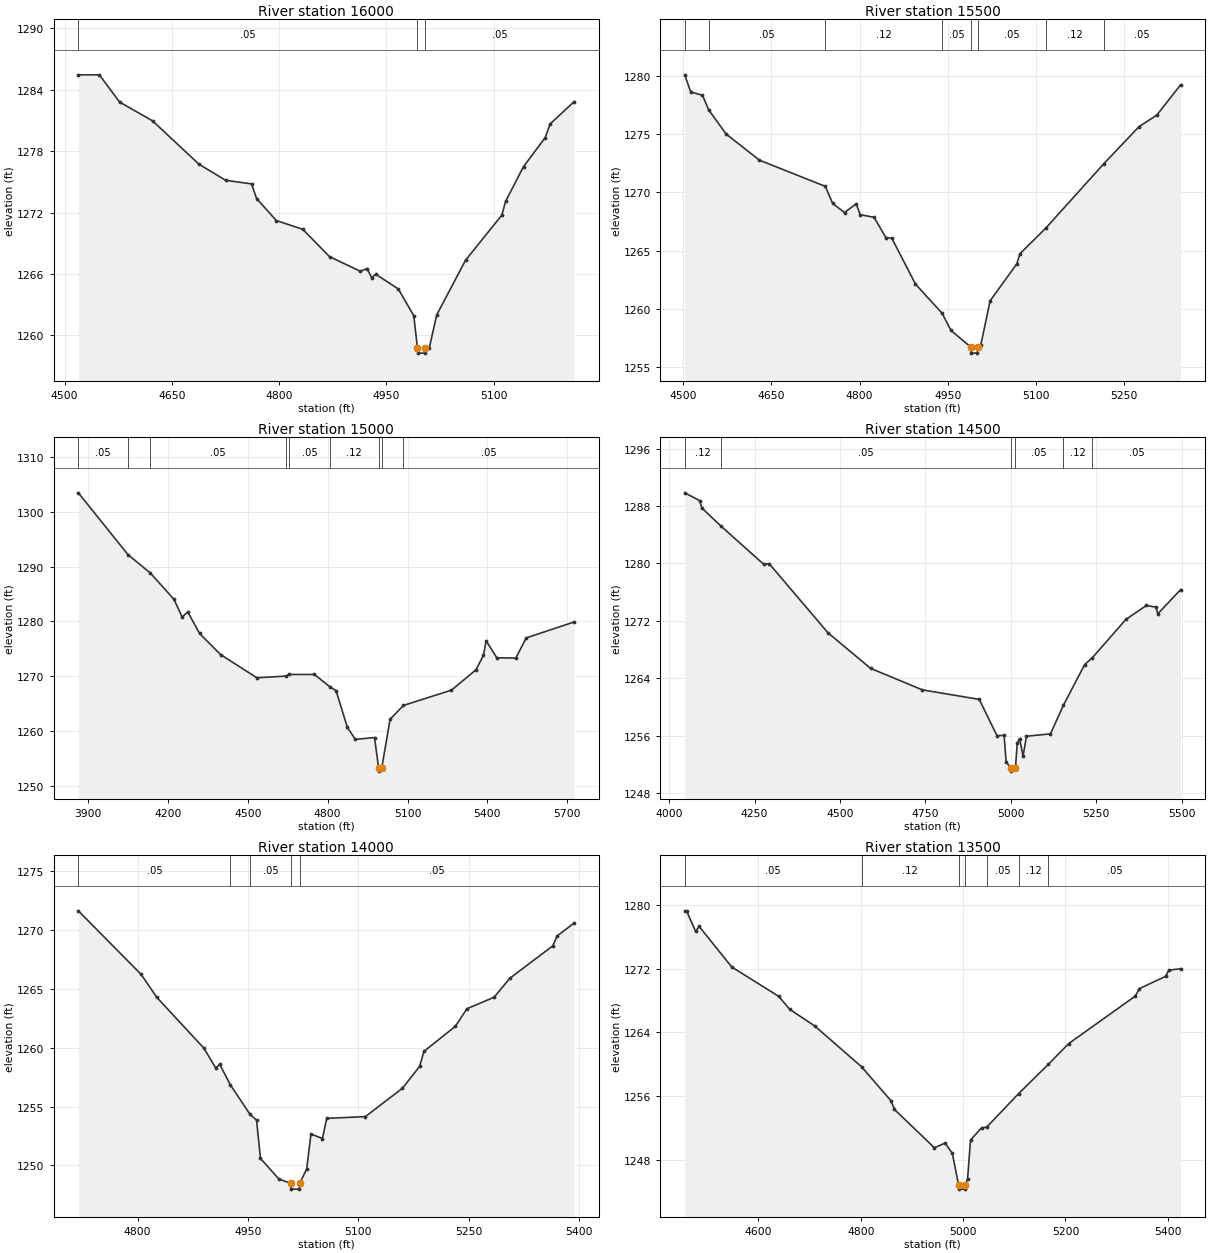
Type RM Length L Ch R = 1 ,16000   ,500,500,500
BEGIN DESCRIPTION:
SAND SPRING CREEK 32.0
END DESCRIPTION:
XS GIS Cut Line= 3
      2774255.67     10277853.09      2774015.68     10277436.36
      2773805.69     10277403.11
#Sta/Elev= 30
  4519.1 1285.46  4548.5 1285.46  4576.8  1282.8  4622.9 1280.96  4687.9 1276.72
  4725.2 1275.15  4761.4  1274.8  4768.4 1273.37    4796 1271.22    4833 1270.36
  4870.4 1267.69  4913.5 1266.26    4923 1266.53  4929.3 1265.62  4935.1 1265.97
  4966.6 1264.53  4988.2 1261.92  4993.4 1258.76  4993.9 1258.26  5004.1 1258.26
  5004.6 1258.76  5010.1 1258.81  5020.2 1261.98  5060.7 1267.35  5111.4 1271.75
  5116.6 1273.09  5141.7 1276.49  5172.1 1279.33  5178.9 1280.66  5212.6 1282.85
#Mann= 3 ,-1 , 0
  4519.1     .05       0  4993.4     .05       0  5004.6     .05       0
Bank Sta=4993.4,5004.6
XS Rating Curve= 0 ,0
Exp/Cntr=0.3,0.1

Type RM Length L Ch R = 1 ,15500   ,500,500,500
BEGIN DESCRIPTION:
SAND SPRING CREEK 31.0
END DESCRIPTION:
XS GIS Cut Line= 3
      2774405.69     10277603.13      2774347.58     10277109.04
      2774005.72     10277053.12
#Sta/Elev= 30
  4502.5 1280.06  4512.6  1278.6  4532.7 1278.31    4543 1277.08    4573 1274.99
  4629.7 1272.75  4741.8 1270.51  4754.2 1269.05  4774.4 1268.27  4794.5 1269.02
  4800.9 1268.09  4824.7 1267.86  4844.9 1266.12  4854.9 1266.07  4895.2 1262.14
  4940.7 1259.63  4955.6 1258.17  4989.8 1256.73  4990.3 1256.23  5000.5 1256.23
    5001 1256.73  5006.4 1256.94  5022.2 1260.71  5067.7 1263.88  5072.9 1264.74
  5116.5 1266.91  5215.9 1272.46  5275.5 1275.62  5305.9 1276.61  5346.4 1279.21
#Mann= 8 ,-1 , 0
  4502.5     .12       0    4543     .05       0  4741.8     .12       0
  4940.7     .05       0  4989.8     .05       0    5001     .05       0
  5116.5     .12       0  5215.9     .05       0
Bank Sta=4989.8,5001
XS Rating Curve= 0 ,0
Exp/Cntr=0.3,0.1

Type RM Length L Ch R = 1 ,15000   ,500,500,500
BEGIN DESCRIPTION:
SAND SPRING CREEK 30.0
END DESCRIPTION:
XS GIS Cut Line= 3
      2775255.67     10277653.09        2774630.     10276704.31
      2773905.65     10276753.11
#Sta/Elev= 30
  3863.5 1303.42  4050.4 1292.15  4133.6 1288.84  4223.2 1284.01  4253.4 1280.79
  4274.5 1281.75  4318.7 1277.83  4397.9 1273.97  4534.3 1269.75  4642.1 1270.06
  4655.9 1270.35  4750.2 1270.36  4806.9 1268.16  4831.5 1267.41  4873.6 1260.78
  4903.8 1258.53    4976 1258.88  4991.5 1253.26    4992 1252.76  5002.8 1253.26
  5034.4  1262.2  5084.7 1264.72  5264.9  1267.5  5357.1 1271.21  5385.2 1273.86
  5395.2 1276.48  5435.3 1273.39  5506.7 1273.34  5545.6 1277.01    5726 1279.92
#Mann= 9 ,-1 , 0
  3863.5     .05       0  4050.4     .12       0  4133.6     .05       0
  4642.1     .12       0  4655.9     .05       0  4806.9     .12       0
  4991.5     .07       0  5002.8     .12       0  5084.7     .05       0
Bank Sta=4991.5,5002.8
XS Rating Curve= 0 ,0
Exp/Cntr=0.3,0.1

Type RM Length L Ch R = 1 ,14500   ,500,500,500
BEGIN DESCRIPTION:
SAND SPRING CREEK 29.0
END DESCRIPTION:
XS GIS Cut Line= 3
      2775455.69     10277203.12      2774941.93     10276398.69
      2774905.68     10275903.11
#Sta/Elev= 30
  4045.5 1289.83  4089.5 1288.74  4095.4 1287.73  4150.3 1285.25  4277.3 1279.85
  4292.5 1279.97  4465.1 1270.32  4589.5 1265.38  4740.9 1262.39  4907.6 1261.06
  4959.2 1256.02  4980.3 1256.04  4986.3 1252.32  4999.8 1251.57  5000.3 1251.07
  5011.4 1251.57  5013.8 1251.76  5018.8    1255  5025.6 1255.61  5035.7 1253.16
  5045.7 1255.93  5115.9 1256.26  5153.7 1260.23  5216.2 1265.92  5238.7 1266.87
  5336.5 1272.19  5396.6 1274.14    5425 1273.91    5430 1272.98  5496.9 1276.35
#Mann= 6 ,-1 , 0
  4045.5     .12       0  4150.3     .05       0  4999.8     .05       0
  5011.4     .05       0  5153.7     .12       0  5238.7     .05       0
Bank Sta=4999.8,5011.4
XS Rating Curve= 0 ,0
Exp/Cntr=0.3,0.1

Type RM Length L Ch R = 1 ,14000   ,500,500,500
BEGIN DESCRIPTION:
SAND SPRING CREEK 28.0
END DESCRIPTION:
XS GIS Cut Line= 3
      2775605.65      10276303.1      2775342.78     10276205.52
      2775005.68     10276003.11
#Sta/Elev= 30
  4719.6 1271.63  4804.9 1266.23  4826.2 1264.28  4890.2 1259.96  4906.3 1258.27
  4911.6  1258.6  4926.2 1256.84  4952.8 1254.34  4961.7 1253.85    4967  1250.6
  4992.1 1248.84  5008.2 1248.49  5008.7 1247.99  5019.8 1247.99  5020.3 1248.49
  5029.8  1249.7  5035.6 1252.67  5051.2 1252.29    5057    1254  5109.5 1254.15
  5159.9 1256.56  5183.2 1258.42  5189.1 1259.69  5231.9 1261.83  5247.4 1263.31
  5284.4 1264.29  5305.7  1265.9    5364 1268.65  5369.9 1269.49  5393.2  1270.6
#Mann= 5 ,-1 , 0
  4719.6     .05       0  4926.2     .12       0  4952.8     .05       0
  5008.2     .05       0  5020.3     .05       0
Bank Sta=5008.2,5020.3
XS Rating Curve= 0 ,0
Exp/Cntr=0.3,0.1

Type RM Length L Ch R = 1 ,13500   ,500,500,500
BEGIN DESCRIPTION:
SAND SPRING CREEK 27.0
END DESCRIPTION:
XS GIS Cut Line= 3
      2776005.67     10276203.09      2775624.77     10275814.41
      2775255.68     10275603.11
#Sta/Elev= 30
  4455.8 1279.25  4459.3 1279.25    4477 1276.67    4484 1277.29  4547.7  1272.2
  4639.6 1268.51  4660.9 1266.89  4710.3 1264.78  4801.7 1259.66  4858.9 1255.41
  4865.9 1254.31  4943.8 1249.51  4964.9 1250.09    4979 1248.79  4991.3 1244.81
  4991.8 1244.31    5003 1244.31  5003.5 1244.81  5008.7 1245.52  5014.5 1250.47
    5036    1252  5046.3  1252.1  5108.5  1256.3  5166.9 1259.99  5206.4 1262.58
  5336.8 1268.55  5344.6 1269.48  5395.8 1271.02  5402.2  1271.8  5425.3 1271.98
#Mann= 7 ,-1 , 0
  4455.8     .05       0  4801.7     .12       0  4991.3     .07       0
  5003.5     .12       0  5046.3     .05       0  5108.5     .12       0
  5166.9     .05       0
Bank Sta=4991.3,5003.5
XS Rating Curve= 0 ,0
Exp/Cntr=0.3,0.1

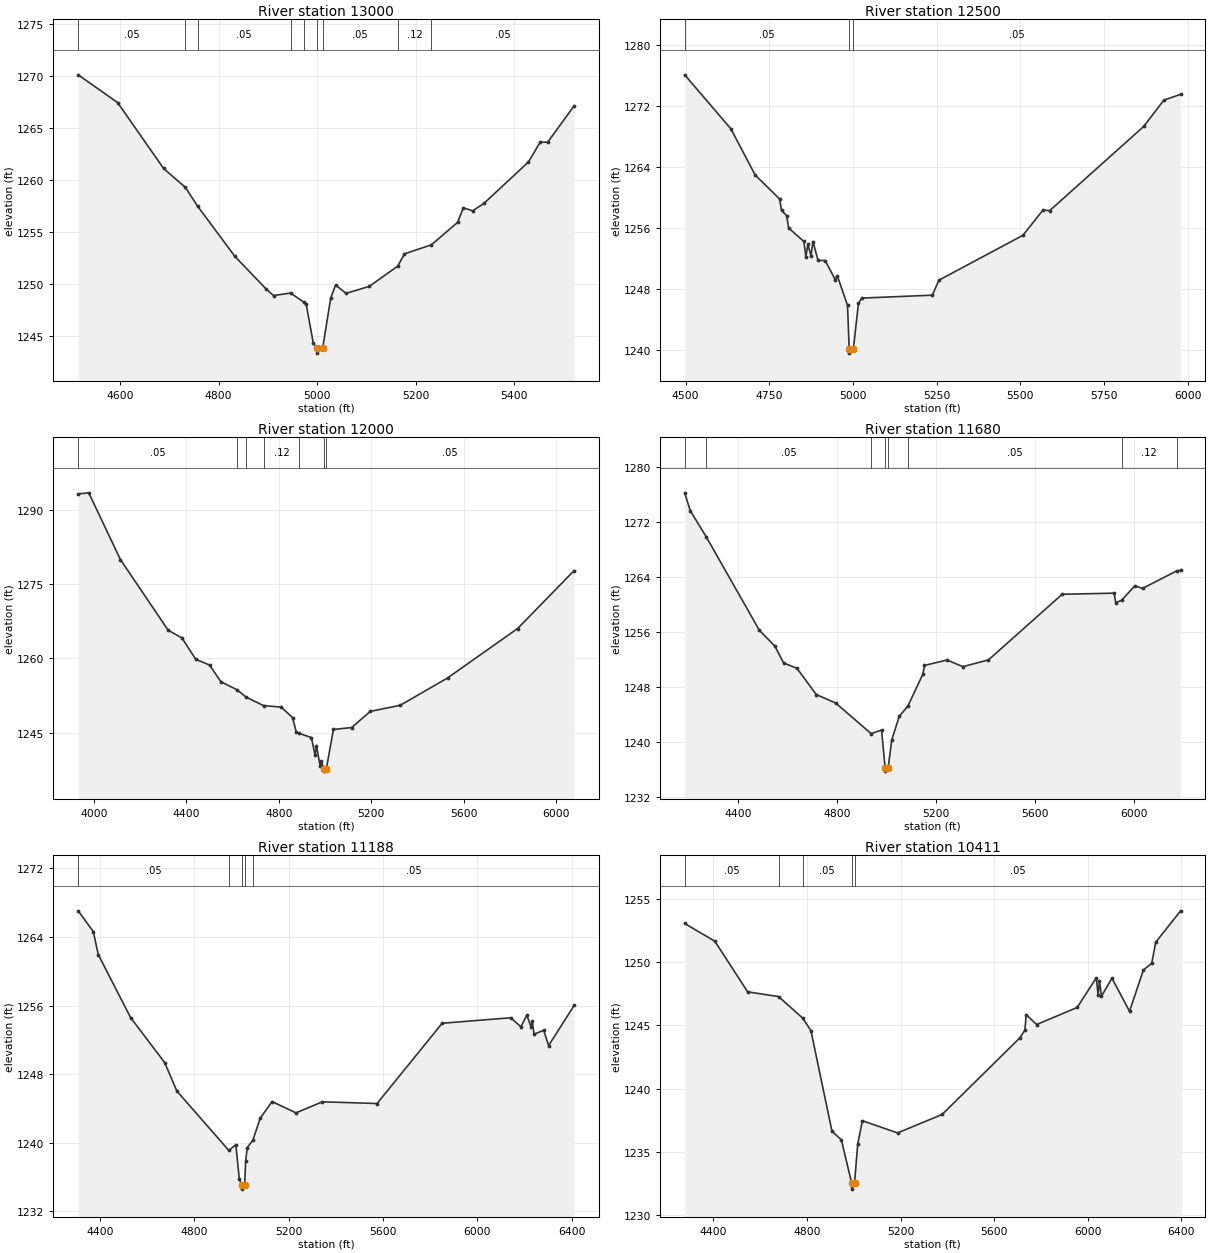
Type RM Length L Ch R = 1 ,13000   ,500,500,500
BEGIN DESCRIPTION:
SAND SPRING CREEK 26.0
END DESCRIPTION:
XS GIS Cut Line= 3
      2776205.68      10275853.1      2775940.49     10275446.78
      2775455.65      10275253.1
#Sta/Elev= 30
  4514.8 1270.14  4594.8 1267.47  4688.3 1261.13  4732.3 1259.32  4757.1 1257.52
  4833.1 1252.67  4896.9 1249.52  4911.5 1248.91    4946 1249.15  4973.7 1248.25
  4977.9 1248.05  4992.4 1244.31  4999.2 1243.87  4999.7 1243.37  5011.4 1243.87
  5027.7 1248.68  5037.5 1249.92    5059 1249.12  5105.9 1249.79  5163.8 1251.74
  5177.5 1252.92  5232.2 1253.79  5285.2 1255.94  5297.1 1257.35    5316 1257.06
    5339 1257.78  5429.1 1261.75  5453.4 1263.68  5468.2 1263.65  5522.1 1267.16
#Mann= 9 ,-1 , 0
  4514.8     .05       0  4732.3     .12       0  4757.1     .05       0
    4946     .12       0  4973.7     .05       0  4999.2     .03       0
  5011.4     .05       0  5163.8     .12       0  5232.2     .05       0
Bank Sta=4999.2,5011.4
XS Rating Curve= 0 ,0
Exp/Cntr=0.3,0.1

Type RM Length L Ch R = 1 ,12500   ,500,500,500
BEGIN DESCRIPTION:
SAND SPRING CREEK 25.0
END DESCRIPTION:
XS GIS Cut Line= 3
       2776705.7     10275353.12      2776281.95     10275082.49
       2775305.7     10275153.11
#Sta/Elev= 30
  4497.2 1276.08  4635.1 1269.02  4707.9 1262.95  4780.6 1259.83  4786.6 1258.32
  4801.8 1257.64  4807.7 1256.02  4853.2 1254.26  4859.3 1252.27  4865.2 1253.88
  4874.5  1252.4  4880.5 1254.23  4895.7 1251.77  4916.8 1251.76  4947.3 1249.24
  4953.2 1249.76  4983.7 1245.89  4988.7 1240.13  4989.2 1239.63    5001 1240.13
  5016.3 1246.16  5026.3 1246.84  5236.9 1247.22  5256.9 1249.19  5507.6 1255.06
  5567.7 1258.37  5587.8  1258.3  5868.5 1269.32  5928.7 1272.76  5978.8 1273.53
#Mann= 3 ,-1 , 0
  4497.2     .05       0  4988.7     .03       0    5001     .05       0
Bank Sta=4988.7,5001
XS Rating Curve= 0 ,0
Exp/Cntr=0.3,0.1

Type RM Length L Ch R = 1 ,12000   ,320,320,320
BEGIN DESCRIPTION:
SAND SPRING CREEK 24.0
END DESCRIPTION:
XS GIS Cut Line= 3
      2777105.64     10275153.09      2776169.74     10274639.21
      2775155.66     10275003.12
#Sta/Elev= 30
  3932.3 1293.18  3977.9 1293.39  4114.8 1279.94  4321.2 1265.69  4380.9 1264.13
  4440.6 1259.83  4500.3 1258.66  4549.6 1255.29  4618.3  1253.7  4659.1 1252.18
  4733.8 1250.49  4810.1 1250.18  4859.4 1248.07  4875.5 1245.13  4889.3 1244.86
  4940.9 1244.04    4957 1240.48  4962.7  1242.4  4978.8  1238.3  4984.5 1239.37
  4993.3 1237.77  4993.8 1237.27  5005.6 1237.77  5036.2 1245.67  5115.5 1246.06
  5195.5 1249.32  5325.4 1250.55  5529.9 1256.06    5833 1266.03  6077.4 1277.72
#Mann= 7 ,-1 , 0
  3932.3     .05       0  4618.3     .12       0  4659.1     .05       0
  4733.8     .12       0  4889.3     .05       0  4993.3     .03       0
  5005.6     .05       0
Bank Sta=4993.3,5005.6
XS Rating Curve= 0 ,0
Exp/Cntr=0.3,0.1

Type RM Length L Ch R = 1 ,11680   ,492,492,492
BEGIN DESCRIPTION:
Mapping XS 26829949
END DESCRIPTION:
XS GIS Cut Line= 4
       2777086.7     10274693.79       2776340.2     10274398.66
      2775888.81     10274311.86      2775178.82     10274536.97
#Sta/Elev= 30
  4182.4  1276.3    4205  1273.7  4270.1 1269.86  4484.6 1256.28  4547.6 1253.96
  4582.7 1251.52  4636.8 1250.73  4715.2 1246.91  4793.6 1245.67  4937.3 1241.21
  4979.2 1241.73  4993.7 1236.25  4994.2 1235.75  5006.1 1236.25  5020.3 1240.29
  5050.8 1243.73  5085.6 1245.22  5147.2 1249.95  5152.6 1251.15  5244.3 1251.94
  5308.1 1250.97    5412 1251.96  5710.3 1261.52  5920.1 1261.68    5927 1260.31
  5950.4 1260.63  6004.1 1262.75  6035.5 1262.37  6174.9 1264.95  6189.6 1264.99
#Mann= 8 ,-1 , 0
  4182.4     .12       0  4270.1     .05       0  4937.3     .12       0
  4993.7     .07       0  5006.1     .12       0  5085.6     .05       0
  5950.4     .12       0  6174.9     .05       0
Bank Sta=4993.7,5006.1
XS Rating Curve= 0 ,0
Exp/Cntr=0.3,0.1

Type RM Length L Ch R = 1 ,11188   ,777,777,777
BEGIN DESCRIPTION:
Mapping XS f097bef9
END DESCRIPTION:
XS GIS Cut Line= 4
      2777347.15     10274259.77      2776635.34     10274051.44
      2776062.42     10273964.63       2775299.9     10274137.93
#Sta/Elev= 30
  4307.6 1267.05  4371.6 1264.63  4392.5 1261.95  4530.1 1254.58  4674.3 1249.34
  4725.9 1246.02  4946.4 1239.08    4976 1239.76  4990.8 1235.73    5001 1235.07
  5001.5 1234.57  5013.4 1235.07  5017.7 1237.81  5024.2 1239.41    5048 1240.26
  5079.3 1242.84  5129.8 1244.79    5231 1243.47  5342.9 1244.76  5574.9 1244.56
    5851 1253.93    6142 1254.57  6185.1 1253.51  6209.9 1254.88  6228.2 1253.48
  6233.3 1254.18  6240.7 1252.65  6281.7 1253.11  6302.2 1251.32  6410.7 1256.01
#Mann= 5 ,-1 , 0
  4307.6     .05       0  4946.4     .12       0    5001     .07       0
  5013.4     .12       0    5048     .05       0
Bank Sta=5001,5013.4
XS Rating Curve= 0 ,0
Exp/Cntr=0.3,0.1

Type RM Length L Ch R = 1 ,10411   ,677,677,677
BEGIN DESCRIPTION:
Mapping XS 7031cd55
END DESCRIPTION:
XS GIS Cut Line= 4
      2777364.48     10273530.61      2776600.62     10273565.33
      2776062.42     10273600.05      2775333.26     10273964.63
#Sta/Elev= 30
  4277.6 1253.04  4406.5 1251.64  4546.7 1247.64  4678.7 1247.27  4781.6 1245.57
    4817 1244.58    4907 1236.64  4947.1 1235.95  4990.9 1232.56  4991.4 1232.06
  5003.4 1232.56  5017.2 1235.65  5037.2 1237.46  5187.5  1236.5  5377.9 1237.96
  5708.9 1243.99  5731.3 1244.61  5736.9 1245.84  5781.6 1245.06  5954.9 1246.41
  6036.3 1248.75  6044.4 1247.39  6049.9 1248.52  6058.7  1247.3  6103.4 1248.72
  6178.5  1246.1  6237.6 1249.36  6273.6 1249.91  6290.3 1251.56  6396.8 1254.04
#Mann= 5 ,-1 , 0
  4277.6     .05       0  4678.7     .12       0  4781.6     .05       0
  4990.9     .05       0  5003.4     .05       0
Bank Sta=4990.9,5003.4
XS Rating Curve= 0 ,0
Exp/Cntr=0.3,0.1

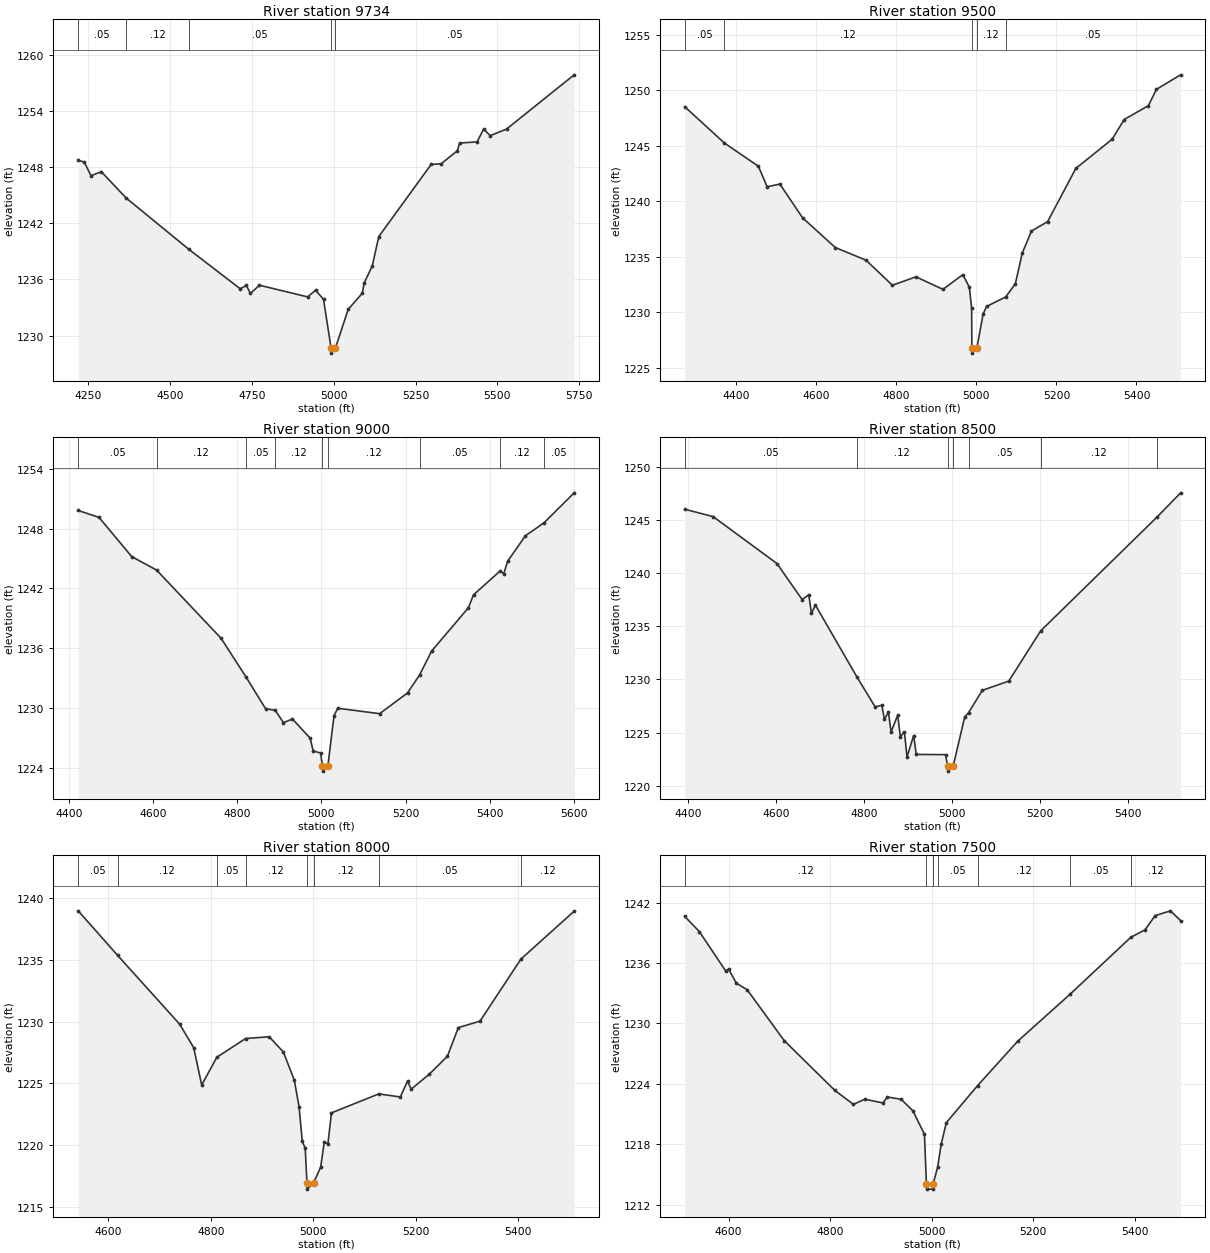
Type RM Length L Ch R = 1 ,9734    ,234,234,234
BEGIN DESCRIPTION:
Mapping XS 3fc65877
END DESCRIPTION:
XS GIS Cut Line= 4
      2777173.56     10273374.36      2776600.62     10273218.11
       2776340.2     10273113.94      2775699.28     10273079.29
#Sta/Elev= 30
  4218.6 1248.75  4237.1 1248.53  4257.9 1247.08    4289 1247.52  4365.2  1244.7
  4556.3 1239.23  4713.9    1235    4733 1235.35    4745  1234.5  4772.7 1235.38
  4920.1 1234.13  4944.4 1234.85  4968.6 1233.86  4991.9 1228.62  4992.4 1228.12
  5004.6 1228.62    5044  1232.8  5087.1 1234.52  5092.7 1235.62  5117.5 1237.42
  5137.5 1240.58  5297.8  1248.3  5327.8 1248.35  5377.9 1249.76  5384.5 1250.58
    5438  1250.7    5458 1252.07    5478 1251.37  5528.1 1252.07  5734.8 1257.87
#Mann= 5 ,-1 , 0
  4218.6     .05       0  4365.2     .12       0  4556.3     .05       0
  4991.9     .05       0  5004.6     .05       0
Bank Sta=4991.9,5004.6
XS Rating Curve= 0 ,0
Exp/Cntr=0.3,0.1

Type RM Length L Ch R = 1 ,9500    ,500,500,500
BEGIN DESCRIPTION:
SAND SPRING CREEK 19.0
END DESCRIPTION:
XS GIS Cut Line= 3
      2777205.64     10273303.09      2776562.53     10272961.49
      2776055.69     10272903.11
#Sta/Elev= 30
  4271.8 1248.53    4371 1245.25  4455.8 1243.16  4477.7 1241.31  4509.5 1241.55
  4566.2 1238.51  4647.9 1235.83  4724.5 1234.69  4790.5 1232.43  4849.2 1233.19
  4916.7 1232.06  4966.3 1233.38  4982.7 1232.25  4988.3 1230.34    4989 1226.81
  4989.5 1226.31  5001.7 1226.81    5017 1229.84  5025.8 1230.52  5073.2 1231.37
  5097.5 1232.56  5114.8 1235.33  5137.8 1237.32    5178 1238.16  5248.5 1242.96
  5339.1 1245.59  5369.3 1247.37  5429.7 1248.62  5449.8 1250.09  5510.2  1251.4
#Mann= 5 ,-1 , 0
  4271.8     .05       0    4371     .12       0    4989     .07       0
  5001.7     .12       0  5073.2     .05       0
Bank Sta=4989,5001.7
XS Rating Curve= 0 ,0
Exp/Cntr=0.3,0.1

Type RM Length L Ch R = 1 ,9000    ,500,500,500
BEGIN DESCRIPTION:
SAND SPRING CREEK 18.0
END DESCRIPTION:
XS GIS Cut Line= 3
      2777355.68      10273203.1        2776958.      10272783.1
      2776455.69     10272453.12
#Sta/Elev= 30
  4421.6 1249.81  4471.1 1249.12  4548.8 1245.19  4607.9 1243.84  4761.2 1237.01
  4820.9 1233.11  4867.2 1229.94    4890 1229.79  4909.7 1228.55  4931.1 1228.91
  4973.2 1226.99  4980.4 1225.71    4998 1225.51  5002.5 1224.19    5003 1223.69
  5015.3 1224.19    5030 1229.26  5038.7 1229.99  5138.5 1229.45  5204.8 1231.53
  5233.7 1233.35    5262 1235.72  5349.5 1240.06  5361.7 1241.36  5424.7 1243.74
  5433.7 1243.48  5442.8 1244.73    5485 1247.27  5529.7 1248.59    5601 1251.58
#Mann= 9 ,-1 , 0
  4421.6     .05       0  4607.9     .12       0  4820.9     .05       0
    4890     .12       0  5002.5     .07       0  5015.3     .12       0
  5233.7     .05       0  5424.7     .12       0  5529.7     .05       0
Bank Sta=5002.5,5015.3
XS Rating Curve= 0 ,0
Exp/Cntr=0.3,0.1

Type RM Length L Ch R = 1 ,8500    ,500,500,500
BEGIN DESCRIPTION:
SAND SPRING CREEK 17.0
END DESCRIPTION:
XS GIS Cut Line= 3
      2777405.67     10272953.09        2777075.     10272442.88
      2776555.72     10272403.11
#Sta/Elev= 30
    4392 1246.02  4456.9 1245.32    4602 1240.91  4659.3 1237.52  4674.5 1237.97
  4680.5 1236.22  4689.6    1237    4784 1230.24  4825.5 1227.43  4840.7 1227.57
  4846.6 1226.27  4855.8 1226.92  4861.8 1225.07  4876.9 1226.65  4882.9  1224.6
  4892.1 1225.09    4898 1222.71  4913.2 1224.73  4919.1 1222.95  4985.7 1222.93
  4990.4 1221.88  4990.9 1221.38  5003.3 1221.88  5029.4 1226.48    5038 1226.87
  5069.5 1228.98  5129.7 1229.85  5202.4 1234.58  5467.1 1245.28  5520.8 1247.56
#Mann= 7 ,-1 , 0
    4392     .05       0    4784     .12       0  4990.4     .07       0
  5003.3     .12       0    5038     .05       0  5202.4     .12       0
  5467.1     .05       0
Bank Sta=4990.4,5003.3
XS Rating Curve= 0 ,0
Exp/Cntr=0.3,0.1

Type RM Length L Ch R = 1 ,8000    ,500,500,500
BEGIN DESCRIPTION:
SAND SPRING CREEK 16.0
END DESCRIPTION:
XS GIS Cut Line= 3
      2777805.65     10272353.09      2777411.75     10272117.25
      2777055.68     10271753.11
#Sta/Elev= 30
  4540.9 1238.99  4617.8 1235.38    4739  1229.8  4766.4  1227.9    4782 1224.87
  4811.6 1227.12  4867.8 1228.64  4913.8 1228.78  4941.4 1227.55  4962.8 1225.28
  4972.1 1223.12  4978.4  1220.3  4984.2 1219.74  4987.5 1216.93    4988 1216.43
  5000.4 1216.93  5014.3 1218.21  5021.3 1220.24  5028.5  1220.1  5035.4 1222.61
  5127.8 1224.15  5169.9  1223.9    5184 1225.19    5191 1224.53  5226.5 1225.75
  5261.8  1227.2  5283.1 1229.52  5325.5 1230.05  5405.4 1235.08  5509.3 1238.96
#Mann= 8 ,-1 , 0
  4540.9     .05       0  4617.8     .12       0  4811.6     .05       0
  4867.8     .12       0  4987.5     .07       0  5000.4     .12       0
  5127.8     .05       0  5405.4     .12       0
Bank Sta=4987.5,5000.4
XS Rating Curve= 0 ,0
Exp/Cntr=0.3,0.1

Type RM Length L Ch R = 1 ,7500    ,500,500,500
BEGIN DESCRIPTION:
SAND SPRING CREEK 15.0
END DESCRIPTION:
XS GIS Cut Line= 3
      2777955.71     10271903.13      2777544.55     10271643.26
      2777055.69     10271603.11
#Sta/Elev= 30
  4513.6 1240.64  4542.5 1239.13  4594.2 1235.23  4600.1  1235.4  4615.4    1234
  4636.6 1233.36  4709.5 1228.31  4809.5 1223.35    4846 1221.97  4868.5 1222.48
    4904 1222.11    4913  1222.7  4940.1 1222.47  4963.2 1221.33  4985.9    1219
  4989.8 1214.05  4990.3 1213.55  5002.4 1213.55  5002.9 1214.05  5011.9 1215.74
  5018.9 1218.03    5029 1220.15  5090.4 1223.82  5169.4 1228.23  5272.6  1232.9
  5392.6 1238.57  5420.3  1239.3  5440.3 1240.71  5470.4 1241.19  5490.5 1240.22
#Mann= 7 ,-1 , 0
  4513.6     .12       0  4989.8     .07       0  5002.9     .12       0
  5011.9     .05       0  5090.4     .12       0  5272.6     .05       0
  5392.6     .12       0
Bank Sta=4989.8,5002.9
XS Rating Curve= 0 ,0
Exp/Cntr=0.3,0.1

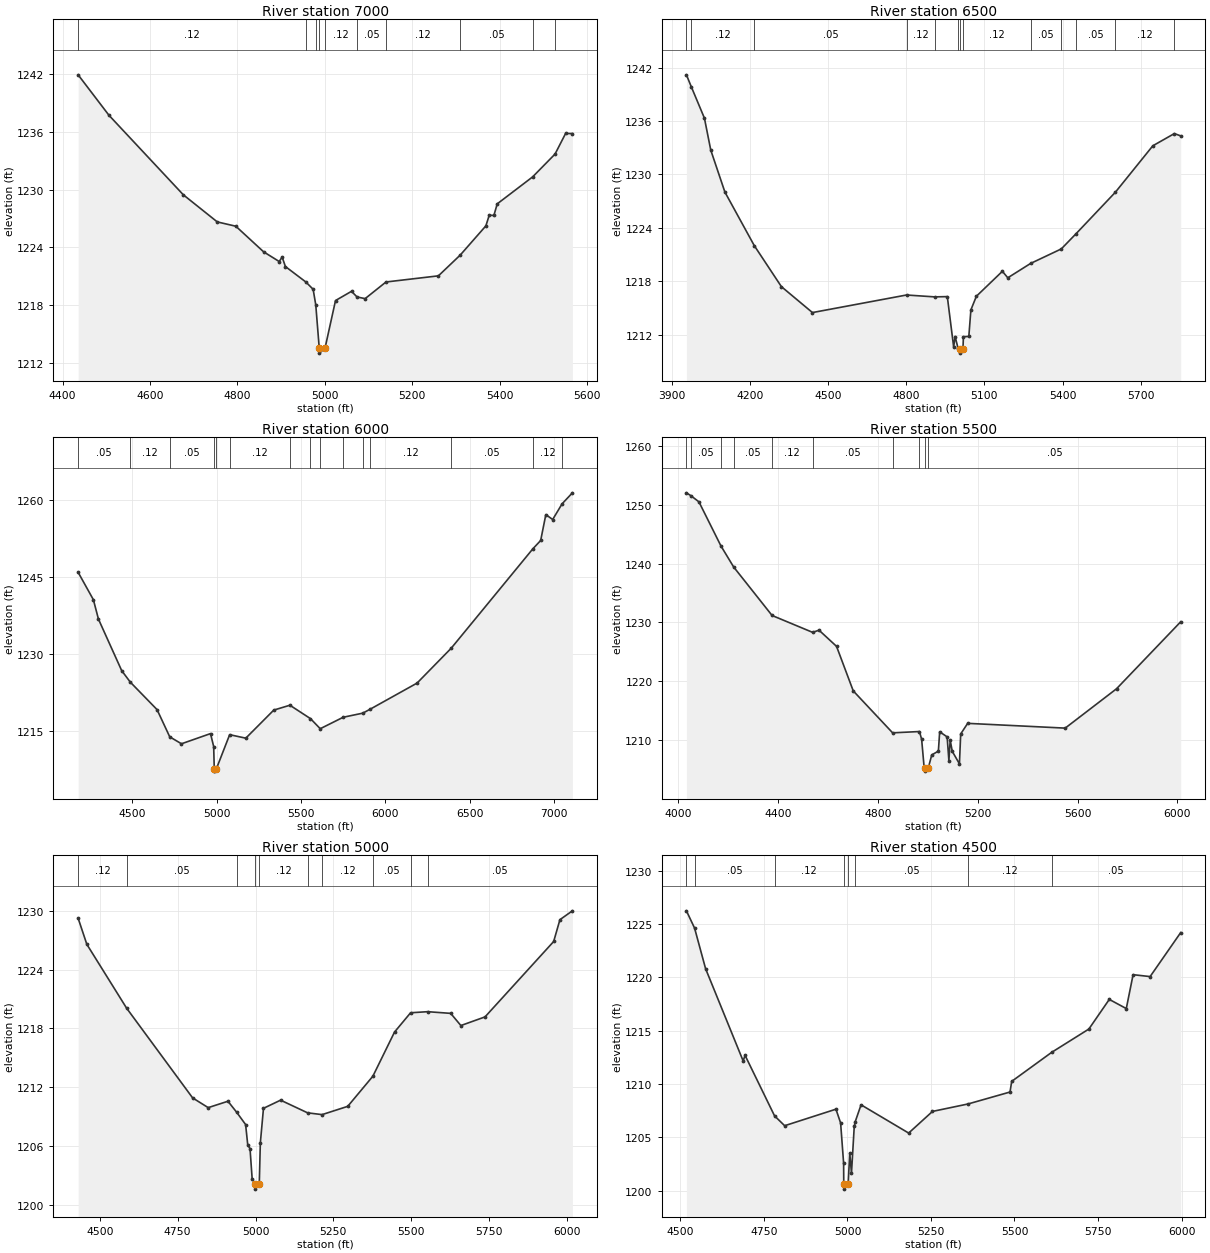
Type RM Length L Ch R = 1 ,7000    ,500,500,500
BEGIN DESCRIPTION:
SAND SPRING CREEK 14.0
END DESCRIPTION:
XS GIS Cut Line= 3
      2778205.72     10271603.14      2777791.69     10271219.43
      2777255.69     10271403.11
#Sta/Elev= 30
  4435.5 1241.94  4506.1 1237.73  4676.2 1229.46  4753.9 1226.64  4796.4 1226.19
  4859.9 1223.53  4895.6 1222.52  4902.4 1222.98  4909.8    1222  4956.6 1220.39
  4973.3 1219.63  4979.3 1218.01  4987.3 1213.49  4987.8 1212.99  5000.4 1213.49
  5024.5 1218.46  5061.1 1219.42  5073.8 1218.83  5092.3 1218.66    5140 1220.39
    5260 1221.03  5309.9 1223.19  5368.6 1226.23  5376.3 1227.34  5386.9 1227.31
  5394.6 1228.52  5475.5 1231.32  5526.9  1233.7    5551 1235.84  5566.6 1235.83
#Mann= 10 ,-1 , 0
  4435.5     .12       0  4956.6     .05       0  4979.3     .12       0
  4987.3     .07       0  5000.4     .12       0  5073.8     .05       0
    5140     .12       0  5309.9     .05       0  5475.5     .12       0
  5526.9     .05       0
Bank Sta=4987.3,5000.4
XS Rating Curve= 0 ,0
Exp/Cntr=0.3,0.1

Type RM Length L Ch R = 1 ,6500    ,500,500,500
BEGIN DESCRIPTION:
SAND SPRING CREEK 13.0
END DESCRIPTION:
XS GIS Cut Line= 3
      2778755.65     10270353.13      2777783.96     10270734.63
      2777105.72     10271253.09
#Sta/Elev= 30
  3956.1 1241.18  3974.4 1239.87  4025.2 1236.32  4049.6 1232.73  4103.8 1228.03
  4216.6 1222.02  4320.7 1217.42  4439.9 1214.51  4801.1 1216.48    4909 1216.27
  4957.7  1216.3  4982.1 1210.64  4987.5 1211.82  4998.7 1210.54  5004.7 1210.46
  5005.2 1209.96  5017.8 1210.46  5019.5  1211.8  5040.3 1211.83  5048.2 1214.81
  5069.3 1216.34  5169.1 1219.14  5189.9 1218.41  5277.4 1220.02  5395.3 1221.65
  5451.8 1223.35  5602.9 1228.01  5746.7 1233.22  5829.4 1234.59  5853.7 1234.33
#Mann= 13 ,-1 , 0
  3956.1     .05       0  3974.4     .12       0  4216.6     .05       0
  4801.1     .12       0    4909     .05       0  4998.7     .12       0
  5004.7     .07       0  5017.8     .12       0  5277.4     .05       0
  5395.3     .12       0  5451.8     .05       0  5602.9     .12       0
  5829.4     .05       0
Bank Sta=5004.7,5017.8
XS Rating Curve= 0 ,0
Exp/Cntr=0.3,0.1

Type RM Length L Ch R = 1 ,6000    ,500,500,500
BEGIN DESCRIPTION:
SAND SPRING CREEK 12.0
END DESCRIPTION:
XS GIS Cut Line= 3
      2778805.66     10270203.11      2777988.85      10270281.9
      2776005.72      10271003.1
#Sta/Elev= 30
  4179.4 1245.91  4269.8 1240.58  4299.9  1236.8  4437.7 1226.78  4488.5 1224.55
  4647.3  1219.2  4722.6  1213.9  4792.2 1212.55  4964.3 1214.53  4983.1 1212.02
  4986.6 1207.73  4987.1 1207.23  4999.7 1207.73  5077.9 1214.32  5173.6 1213.64
  5339.3  1219.1  5435.1 1220.05  5557.2 1217.44    5615 1215.48    5751 1217.71
  5867.3 1218.51  5912.3  1219.3  6189.2 1224.36  6391.8 1231.15  6875.7 1250.48
    6922  1252.1  6952.6 1257.13  6993.2 1256.18    7049 1259.23  7110.2 1261.37
#Mann= 15 ,-1 , 0
  4179.4     .05       0  4488.5     .12       0  4722.6     .05       0
  4986.6     .05       0  4999.7     .05       0  5077.9     .12       0
  5435.1     .05       0  5557.2     .12       0    5615     .05       0
    5751     .12       0  5867.3     .05       0  5912.3     .12       0
  6391.8     .05       0  6875.7     .12       0    7049     .05       0
Bank Sta=4986.6,4999.7
XS Rating Curve= 0 ,0
Exp/Cntr=0.3,0.1

Type RM Length L Ch R = 1 ,5500    ,500,500,500
BEGIN DESCRIPTION:
SAND SPRING CREEK 11.0
END DESCRIPTION:
XS GIS Cut Line= 3
      2778905.64     10270153.11      2777940.93     10270088.16
      2776955.68     10269853.11
#Sta/Elev= 30
  4033.1 1252.01  4050.5 1251.54  4083.2 1250.48  4171.4 1242.99  4222.3 1239.42
  4376.2 1231.19  4538.3 1228.33  4564.3 1228.69  4634.4 1225.95  4701.3 1218.39
    4859 1211.27  4966.4 1211.49  4975.2 1210.19  4985.2 1205.42  4988.6 1205.27
  4989.1 1204.77  5001.7 1205.27  5015.7 1207.52  5042.3 1208.17  5047.5 1211.45
  5077.4 1210.58  5084.4 1206.54  5089.6 1210.03  5097.9 1208.13  5126.6 1206.01
  5131.7 1211.08  5159.6 1212.88  5550.3 1212.07  5755.9 1218.75  6012.9 1230.12
#Mann= 10 ,-1 , 0
  4033.1     .12       0  4050.5     .05       0  4171.4     .12       0
  4222.3     .05       0  4376.2     .12       0  4538.3     .05       0
    4859     .12       0  4966.4     .05       0  4988.6     .05       0
  5001.7     .05       0
Bank Sta=4988.6,5001.7
XS Rating Curve= 0 ,0
Exp/Cntr=0.3,0.1

Type RM Length L Ch R = 1 ,5000    ,500,500,500
BEGIN DESCRIPTION:
SAND SPRING CREEK 10.0
END DESCRIPTION:
XS GIS Cut Line= 3
      2778355.66     10270053.08      2777971.19     10269632.53
      2776955.64     10269703.11
#Sta/Elev= 30
  4430.2 1229.22  4458.2 1226.56  4586.1 1220.06    4798 1210.94    4848 1209.95
  4911.5  1210.6  4939.7 1209.47  4968.2 1208.23    4975 1206.18  4982.4 1205.77
  4989.2 1202.72  4998.9 1202.16  4999.4 1201.66  5012.1 1202.16  5015.5 1206.35
  5025.6 1209.88  5080.6 1210.71  5167.4 1209.42  5213.9 1209.24  5296.2 1210.08
  5377.1 1213.15  5446.6 1217.64  5498.2  1219.6    5553 1219.71    5627 1219.54
  5659.7  1218.3  5737.3 1219.18  5957.8 1226.85  5977.9 1229.07    6018 1229.97
#Mann= 10 ,-1 , 0
  4430.2     .12       0  4586.1     .05       0  4939.7     .12       0
  4998.9     .07       0  5012.1     .12       0  5167.4     .05       0
  5213.9     .12       0  5377.1     .05       0  5498.2     .12       0
    5553     .05       0
Bank Sta=4998.9,5012.1
XS Rating Curve= 0 ,0
Exp/Cntr=0.3,0.1

Type RM Length L Ch R = 1 ,4500    ,500,500,500
BEGIN DESCRIPTION:
SAND SPRING CREEK 9.0
END DESCRIPTION:
XS GIS Cut Line= 3
      2778555.69     10269403.12      2778135.66     10269166.49
      2777155.67     10269353.11
#Sta/Elev= 30
  4517.9 1226.25  4542.3 1224.63  4575.3 1220.82  4687.7 1212.17  4693.5 1212.69
  4781.8 1207.01    4812 1206.09  4965.5 1207.64  4979.5 1206.35  4988.5 1202.57
  4988.9 1200.64  4989.4 1200.14  5002.1 1200.64  5006.9 1203.53    5012 1201.62
  5020.3 1206.02  5023.4 1206.48  5040.7 1208.05  5183.2  1205.4  5254.5 1207.43
    5361 1208.13  5486.6 1209.25  5491.7 1210.25  5611.2 1212.97  5722.7 1215.16
  5783.8 1217.94  5834.7 1217.08  5855.1 1220.26    5906 1220.08  5997.6 1224.21
#Mann= 8 ,-1 , 0
  4517.9     .12       0  4542.3     .05       0  4781.8     .12       0
  4988.9     .07       0  5002.1     .12       0  5023.4     .05       0
    5361     .12       0  5611.2     .05       0
Bank Sta=4988.9,5002.1
XS Rating Curve= 0 ,0
Exp/Cntr=0.3,0.1

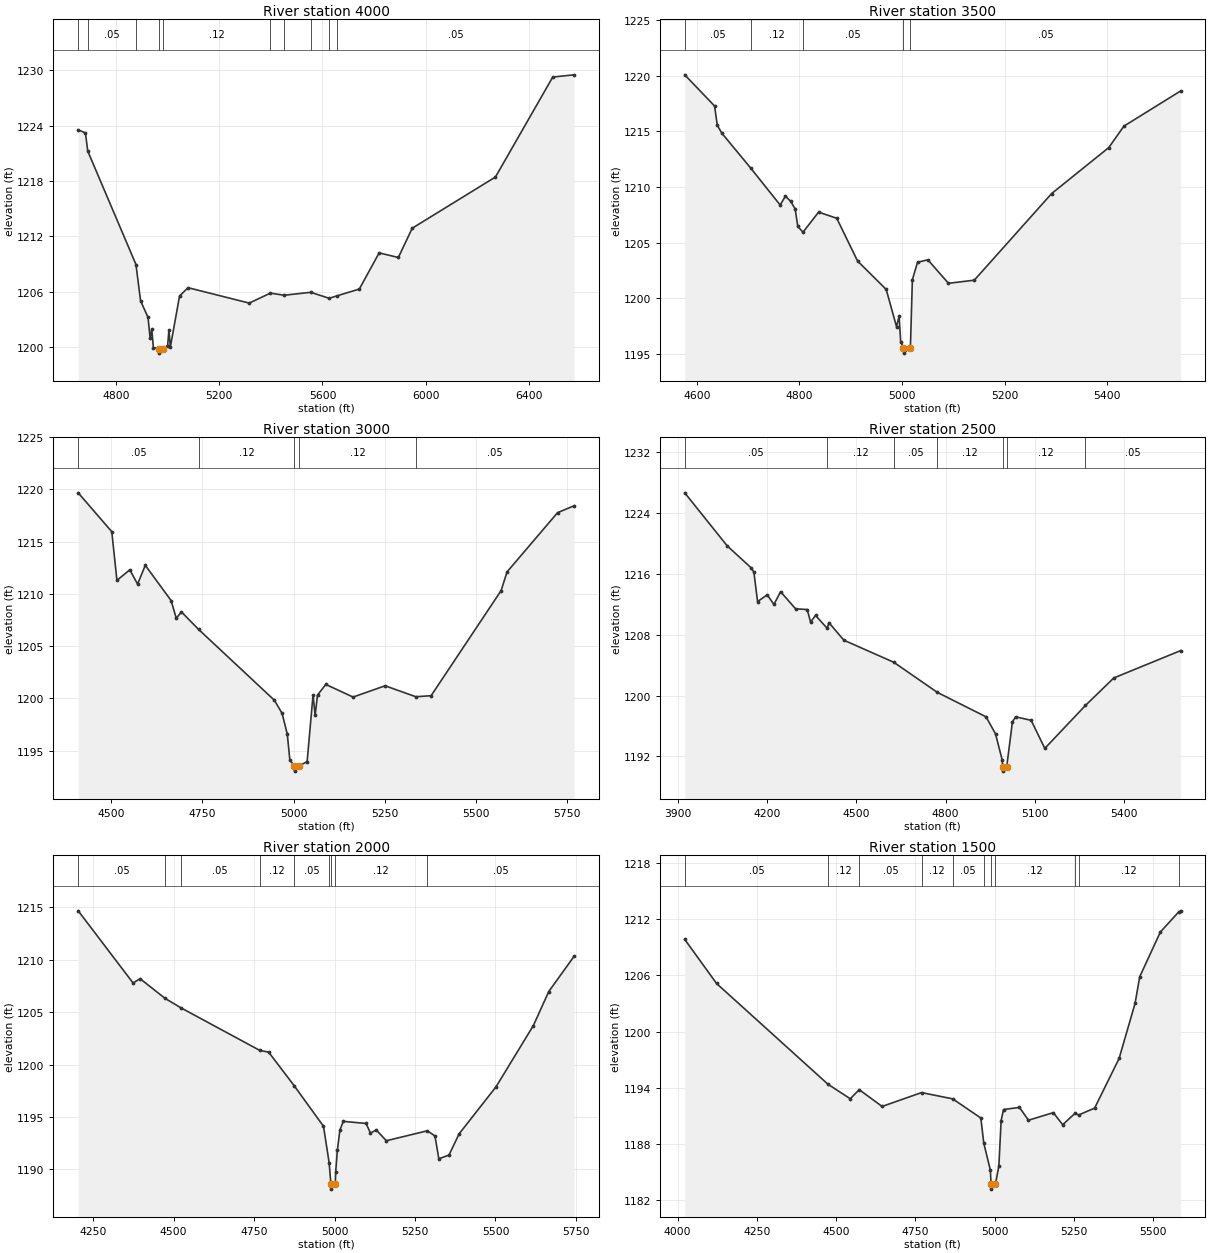
Type RM Length L Ch R = 1 ,4000    ,500,500,500
BEGIN DESCRIPTION:
SAND SPRING CREEK 8.0
END DESCRIPTION:
XS GIS Cut Line= 3
      2778755.67     10268603.13      2778482.31     10268815.89
      2776955.65     10269203.12
#Sta/Elev= 30
  4653.6 1223.52  4681.6  1223.2  4690.5 1221.23  4877.4 1208.94  4895.2 1205.01
  4924.1 1203.21  4932.3 1200.94  4938.6 1201.93    4945 1199.93  4967.2 1199.84
  4967.7 1199.34  4980.5 1199.84    5000 1200.16  5005.3 1201.87  5010.5 1199.98
  5046.3 1205.53  5079.1 1206.43  5316.3 1204.76  5398.1 1205.84  5451.7 1205.61
  5554.7 1205.93    5626 1205.28  5657.8 1205.56  5742.8 1206.28  5819.6  1210.2
  5894.1  1209.7  5947.7 1212.87  6270.3 1218.42  6492.4 1229.25    6575 1229.49
#Mann= 10 ,-1 , 0
  4653.6     .12       0  4690.5     .05       0  4877.4     .12       0
  4967.2     .07       0  4980.5     .12       0  5398.1     .05       0
  5451.7     .12       0  5554.7     .05       0    5626     .12       0
  5657.8     .05       0
Bank Sta=4967.2,4980.5
XS Rating Curve= 0 ,0
Exp/Cntr=0.3,0.1

Type RM Length L Ch R = 1 ,3500    ,500,500,500
BEGIN DESCRIPTION:
SAND SPRING CREEK 7.0
END DESCRIPTION:
XS GIS Cut Line= 3
      2778705.71     10268503.12      2778296.02     10268396.62
      2777755.67     10268453.11
#Sta/Elev= 30
  4576.7 1220.08  4634.9 1217.28  4640.1 1215.56    4649 1214.84  4705.2 1211.71
  4762.7 1208.39    4773 1209.19  4783.4 1208.71  4791.9 1208.04  4797.1 1206.47
  4807.2 1205.95  4837.6 1207.75    4873  1207.2  4913.6 1203.36  4969.4 1200.81
  4989.5 1197.47  4994.6 1198.41  4997.6 1196.12    5003 1195.59  5003.5 1195.09
  5016.6 1195.59  5020.4 1201.68  5030.5 1203.25  5050.6 1203.47  5090.8 1201.36
  5141.1 1201.64  5291.9 1209.42  5403.3 1213.55  5432.7 1215.47  5543.3 1218.63
#Mann= 5 ,-1 , 0
  4576.7     .05       0  4705.2     .12       0  4807.2     .05       0
    5003     .03       0  5016.6     .05       0
Bank Sta=5003,5016.6
XS Rating Curve= 0 ,0
Exp/Cntr=0.3,0.1

Type RM Length L Ch R = 1 ,3000    ,500,500,500
BEGIN DESCRIPTION:
SAND SPRING CREEK 6.0
END DESCRIPTION:
XS GIS Cut Line= 3
      2778805.69     10268353.12      2778383.34     10267940.72
      2777705.66     10268303.13
#Sta/Elev= 30
  4409.7 1219.68  4501.7 1215.96  4515.8  1211.3  4551.1 1212.31  4572.4 1210.94
  4593.5 1212.74  4664.2 1209.37  4678.4 1207.67  4692.5 1208.28  4739.5 1206.61
  4947.1 1199.83  4968.4 1198.57  4982.6 1196.59  4989.6 1194.11  5001.9 1193.54
  5002.4 1193.04  5015.5 1193.54    5037 1193.96  5053.2 1200.35  5058.9 1198.37
  5065.4 1200.32  5088.1 1201.34  5162.9 1200.13  5250.7 1201.21  5334.9 1200.16
  5376.7 1200.26  5568.5 1210.32  5584.8 1212.11  5723.1 1217.78  5768.5 1218.44
#Mann= 5 ,-1 , 0
  4409.7     .05       0  4739.5     .12       0  5001.9     .07       0
  5015.5     .12       0  5334.9     .05       0
Bank Sta=5001.9,5015.5
XS Rating Curve= 0 ,0
Exp/Cntr=0.3,0.1

Type RM Length L Ch R = 1 ,2500    ,500,500,500
BEGIN DESCRIPTION:
SAND SPRING CREEK 5.0
END DESCRIPTION:
XS GIS Cut Line= 3
      2778905.66     10268453.07      2778428.52     10267485.97
      2778181.57     10266948.49
#Sta/Elev= 30
  3921.6 1226.66  4064.7 1219.68  4144.6 1216.82  4154.5 1216.23  4166.9 1212.36
  4199.4 1213.25  4221.9 1211.98  4244.3 1213.66  4294.8 1211.41  4334.1 1211.31
  4345.3 1209.67  4362.1 1210.54  4401.5 1208.83    4407 1209.59  4457.5 1207.28
  4625.4 1204.38  4772.1 1200.42  4936.3  1197.2  4968.3 1194.95  4990.8  1191.5
    4992 1190.56  4992.5 1190.06  5005.6 1190.56  5025.2 1196.56  5036.2  1197.2
  5088.2 1196.74  5134.1 1193.05  5271.1  1198.7  5366.3 1202.31  5591.5 1205.91
#Mann= 7 ,-1 , 0
  3921.6     .05       0  4401.5     .12       0  4625.4     .05       0
  4772.1     .12       0    4992     .07       0  5005.6     .12       0
  5271.1     .05       0
Bank Sta=4992,5005.6
XS Rating Curve= 0 ,0
Exp/Cntr=0.3,0.1

Type RM Length L Ch R = 1 ,2000    ,500,500,500
BEGIN DESCRIPTION:
SAND SPRING CREEK 4.0
END DESCRIPTION:
XS GIS Cut Line= 3
      2778905.68     10268053.06      2778842.56     10267258.87
       2778605.7     10266553.16
#Sta/Elev= 30
  4203.3 1214.68  4373.8 1207.79  4395.7  1208.2  4472.9 1206.33  4521.3 1205.44
  4767.8 1201.35  4795.1 1201.19  4874.1    1198  4965.6 1194.11  4983.1 1190.64
  4988.6 1188.61  4989.1 1188.11  5002.2 1188.61  5003.4 1189.71  5008.6  1191.8
  5016.6 1193.76  5027.2 1194.58    5098 1194.38  5111.6 1193.46  5129.5 1193.76
    5161 1192.73  5288.4 1193.68    5312 1193.19    5324 1191.01  5355.5 1191.36
  5387.1 1193.39  5501.8 1197.88  5617.9 1203.73  5665.6 1206.97  5744.4 1210.34
#Mann= 9 ,-1 , 0
  4203.3     .05       0  4472.9     .12       0  4521.3     .05       0
  4767.8     .12       0  4874.1     .05       0  4983.1     .12       0
  4988.6     .07       0  5002.2     .12       0  5288.4     .05       0
Bank Sta=4988.6,5002.2
XS Rating Curve= 0 ,0
Exp/Cntr=0.3,0.1

Type RM Length L Ch R = 1 ,1500    ,523,523,523
BEGIN DESCRIPTION:
SAND SPRING CREEK 3.0
END DESCRIPTION:
XS GIS Cut Line= 3
      2779105.68     10267903.11      2779198.09     10266930.09
      2778855.66     10266453.07
#Sta/Elev= 30
  4022.6 1209.84    4123 1205.14  4474.9 1194.38  4544.9 1192.84  4573.1 1193.81
  4645.4 1192.02  4769.7  1193.5    4868 1192.83  4956.8 1190.79  4966.2 1188.09
  4986.9 1185.23  4989.1  1183.7  4989.6  1183.2  5002.8  1183.7  5013.7 1185.67
  5020.9 1190.52  5028.4 1191.69  5078.8 1191.92  5107.1 1190.55  5185.6 1191.36
  5215.1 1190.07  5254.2 1191.29  5265.2 1191.11  5315.8 1191.84  5393.1 1197.14
  5443.5 1203.02  5458.2 1205.86  5523.3 1210.63  5581.1 1212.77  5587.2 1212.89
#Mann= 11 ,-1 , 0
  4022.6     .05       0  4474.9     .12       0  4573.1     .05       0
  4769.7     .12       0    4868     .05       0  4966.2     .12       0
  4989.1     .07       0  5002.8     .12       0  5254.2     .05       0
  5265.2     .12       0  5581.1     .05       0
Bank Sta=4989.1,5002.8
XS Rating Curve= 0 ,0
Exp/Cntr=0.3,0.1