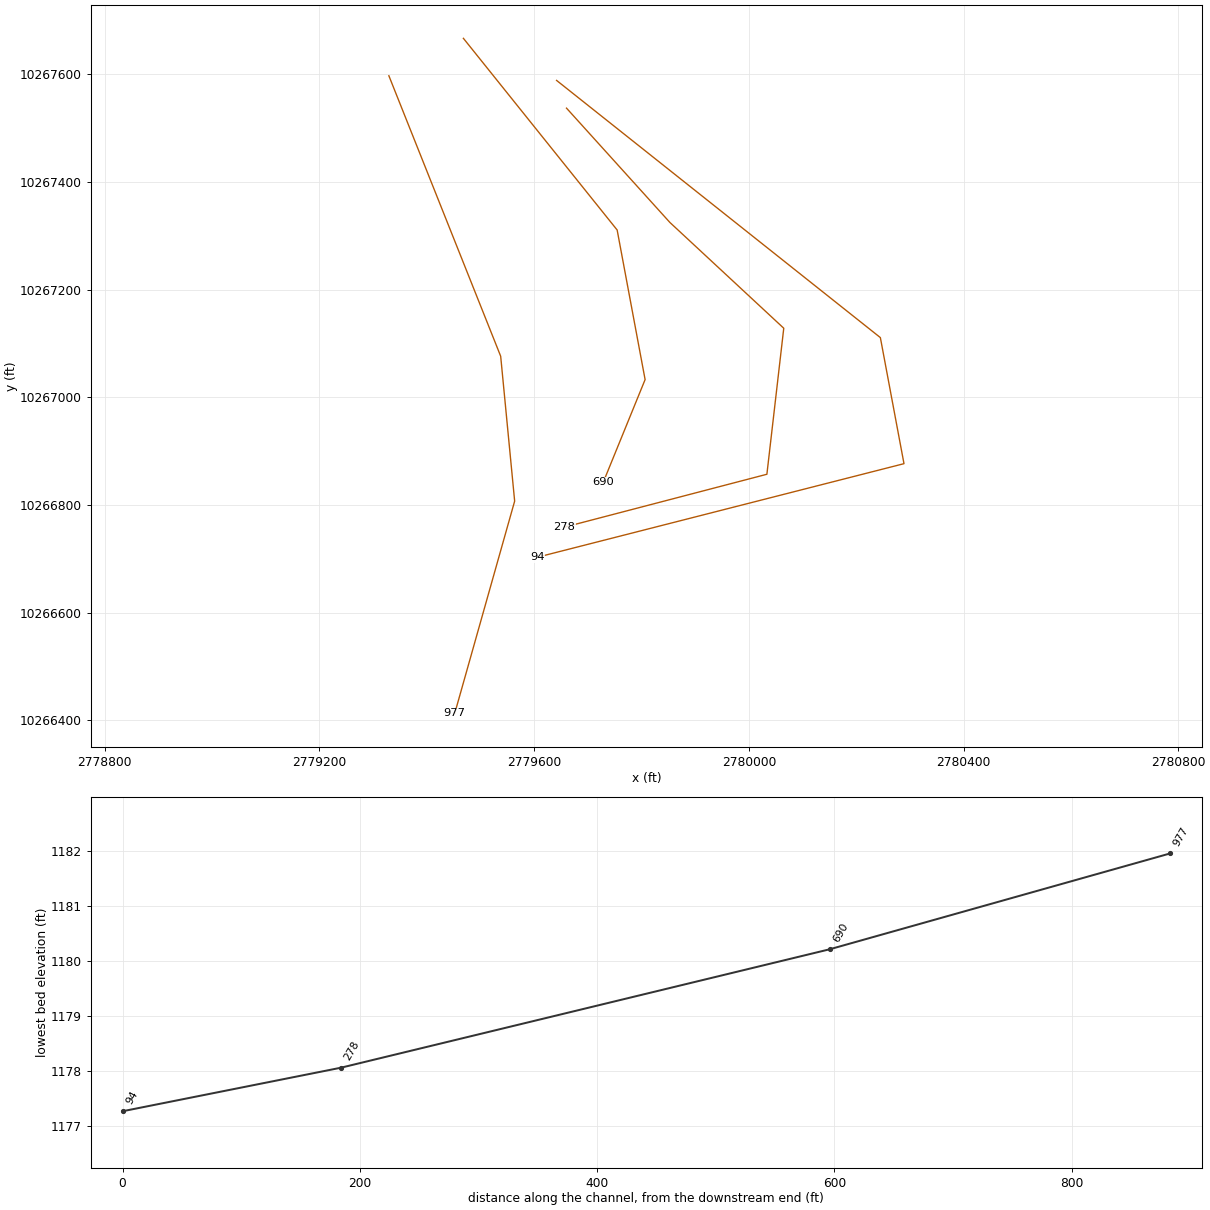
HEC-RAS study SAND SPRING CREEK.prj: SAND SPRING CREEK Base Level Engineering

--- SAND SPRING CREEK.g01 (geometry) --- (continued)

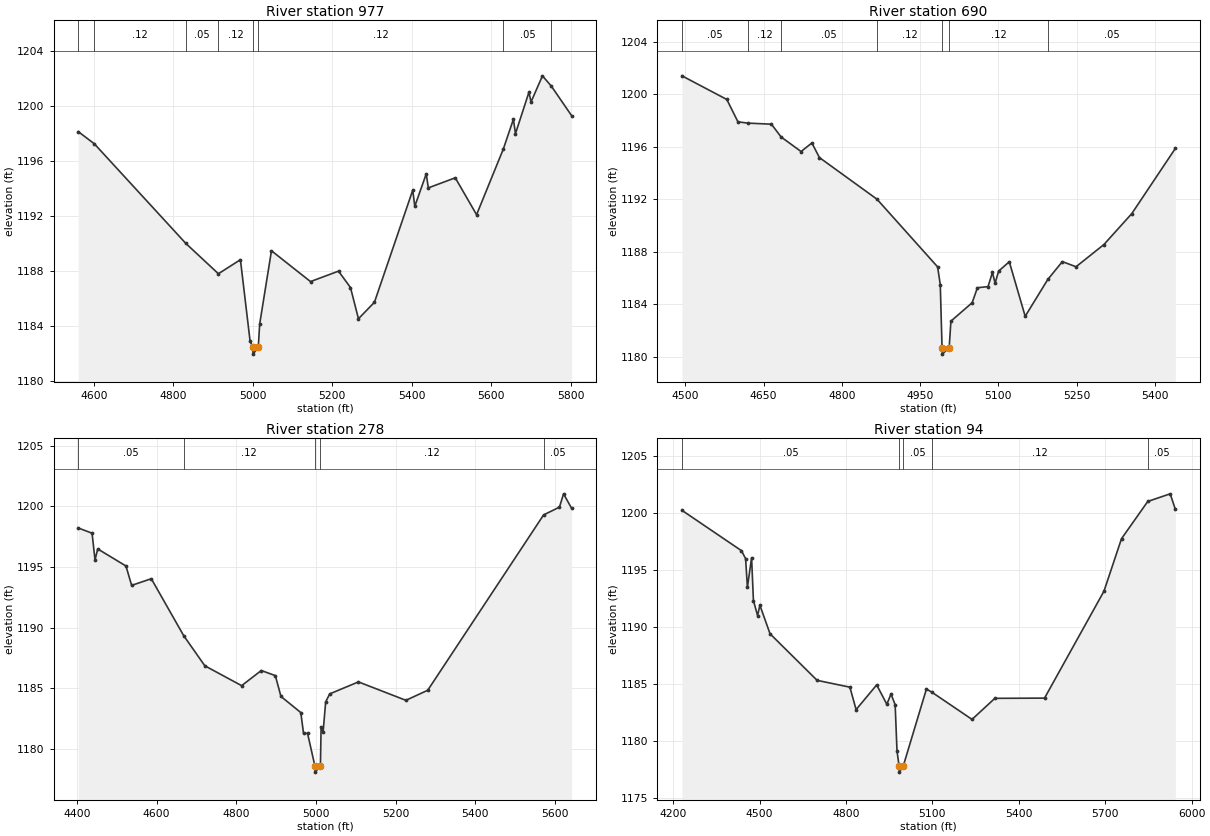
Type RM Length L Ch R = 1 ,977     ,287,287,287
BEGIN DESCRIPTION:
Mapping XS 9b74772a
END DESCRIPTION:
XS GIS Cut Line= 4
      2779329.25     10267597.23      2779537.57     10267076.43
      2779563.61     10266807.33      2779451.98     10266413.21
#Sta/Elev= 30
  4560.8 1198.12  4601.4 1197.23  4831.3    1190  4913.4 1187.79  4968.8 1188.81
  4993.1  1182.9    5000 1182.45  5000.5 1181.95  5013.7 1182.45  5017.3 1184.15
  5046.9 1189.46  5145.1 1187.22  5215.5 1187.98  5245.6 1186.79  5265.7 1184.52
  5305.9 1185.72  5402.2 1193.86  5407.4 1192.69  5436.2 1195.05  5441.4 1194.03
  5509.2 1194.76  5562.8 1192.08  5629.9 1196.84  5655.4 1199.01  5660.6 1197.97
  5694.5 1200.98  5699.7 1200.27  5728.5 1202.17  5751.1 1201.41  5801.7 1199.28
#Mann= 8 ,-1 , 0
  4560.8     .05       0  4601.4     .12       0  4831.3     .05       0
  4913.4     .12       0    5000     .07       0  5013.7     .12       0
  5629.9     .05       0  5751.1     .12       0
Bank Sta=5000,5013.7
XS Rating Curve= 0 ,0
Exp/Cntr=0.3,0.1

Type RM Length L Ch R = 1 ,690     ,412,412,412
BEGIN DESCRIPTION:
Mapping XS 813bfc22
END DESCRIPTION:
XS GIS Cut Line= 4
      2779468.11     10267666.72      2779754.58      10267310.8
      2779806.67     10267033.02      2779728.55     10266842.08
#Sta/Elev= 30
  4493.6 1201.39  4579.6 1199.59  4600.9 1197.89  4619.9 1197.79  4665.1 1197.71
  4683.6 1196.74  4721.9 1195.63  4742.7 1196.28  4757.1 1195.17  4867.5    1192
  4983.7 1186.85  4988.8  1185.5  4992.2 1180.71  4992.7 1180.21  5005.9 1180.71
  5009.2 1182.72  5049.9 1184.12    5060 1185.26  5080.4 1185.35  5088.8 1186.43
  5093.9 1185.61  5100.7 1186.53  5121.1 1187.24  5151.6 1183.09  5194.9 1185.89
  5222.8 1187.25  5249.1 1186.86  5302.5 1188.55  5355.9  1190.9  5439.4 1195.86
#Mann= 7 ,-1 , 0
  4493.6     .05       0  4619.9     .12       0  4683.6     .05       0
  4867.5     .12       0  4992.2     .07       0  5005.9     .12       0
  5194.9     .05       0
Bank Sta=4992.2,5005.9
XS Rating Curve= 0 ,0
Exp/Cntr=0.3,0.1

Type RM Length L Ch R = 1 ,278     ,184,184,184
BEGIN DESCRIPTION:
Mapping XS 2a546d40
END DESCRIPTION:
XS GIS Cut Line= 5
      2779660.24     10267537.09       2779852.8     10267324.88
      2780065.01     10267128.39      2780033.57     10266857.24
      2779656.28     10266758.99
#Sta/Elev= 30
  4403.4 1198.22  4438.2 1197.79  4445.6 1195.58  4452.4 1196.49  4523.3 1195.08
  4537.5 1193.48  4586.9 1194.03    4668 1189.34  4721.3 1186.84  4813.7  1185.2
    4863 1186.45  4898.3 1186.03  4912.4 1184.31  4962.2 1182.98  4969.1 1181.26
  4979.2 1181.26  4997.7 1178.56  4998.2 1178.06  5011.5 1178.56  5013.2 1181.79
  5018.2 1181.37  5024.7 1183.86  5034.8 1184.52  5106.9 1185.51  5226.1 1183.99
  5280.9 1184.82  5571.8  1199.3  5611.6 1199.94  5621.9 1201.04    5642 1199.85
#Mann= 5 ,-1 , 0
  4403.4     .05       0    4668     .12       0  4997.7     .07       0
  5011.5     .12       0  5571.8     .05       0
Bank Sta=4997.7,5011.5
XS Rating Curve= 0 ,0
Exp/Cntr=0.3,0.1

Type RM Length L Ch R = 1 ,94      ,0,0,0
BEGIN DESCRIPTION:
SAND SPRING CREEK 2.0
END DESCRIPTION:
XS GIS Cut Line= 4
      2779641.75     10267588.57        2780245.       10267111.
        2780289.     10266876.89      2779605.66     10266703.11
#Sta/Elev= 30
  4230.6 1200.26    4437 1196.72  4451.5 1196.02  4457.8  1193.5  4472.3  1196.1
  4478.7 1192.34  4493.1 1191.02  4501.1 1191.93  4536.4 1189.42  4699.8 1185.33
  4813.6 1184.73  4835.1 1182.76  4906.6 1184.93  4941.8 1183.23  4956.3 1184.13
  4970.7 1183.19  4977.1 1179.14  4984.6 1177.77  4985.1 1177.27  4998.4 1177.77
  5079.3 1184.57  5098.1 1184.29  5237.6  1181.9  5316.7 1183.75  5489.3 1183.77
  5695.6 1193.16  5756.5 1197.77  5847.6 1201.04  5925.4 1201.71  5943.3 1200.36
#Mann= 5 ,-1 , 0
  4230.6     .05       0  4984.6     .03       0  4998.4     .05       0
  5098.1     .12       0  5847.6     .05       0
Bank Sta=4984.6,4998.4
XS Rating Curve= 0 ,0
Exp/Cntr=0.3,0.1

Chan Stop Cuts=-1
Use User Specified Reach Order=0
Composite Channel Slope=5