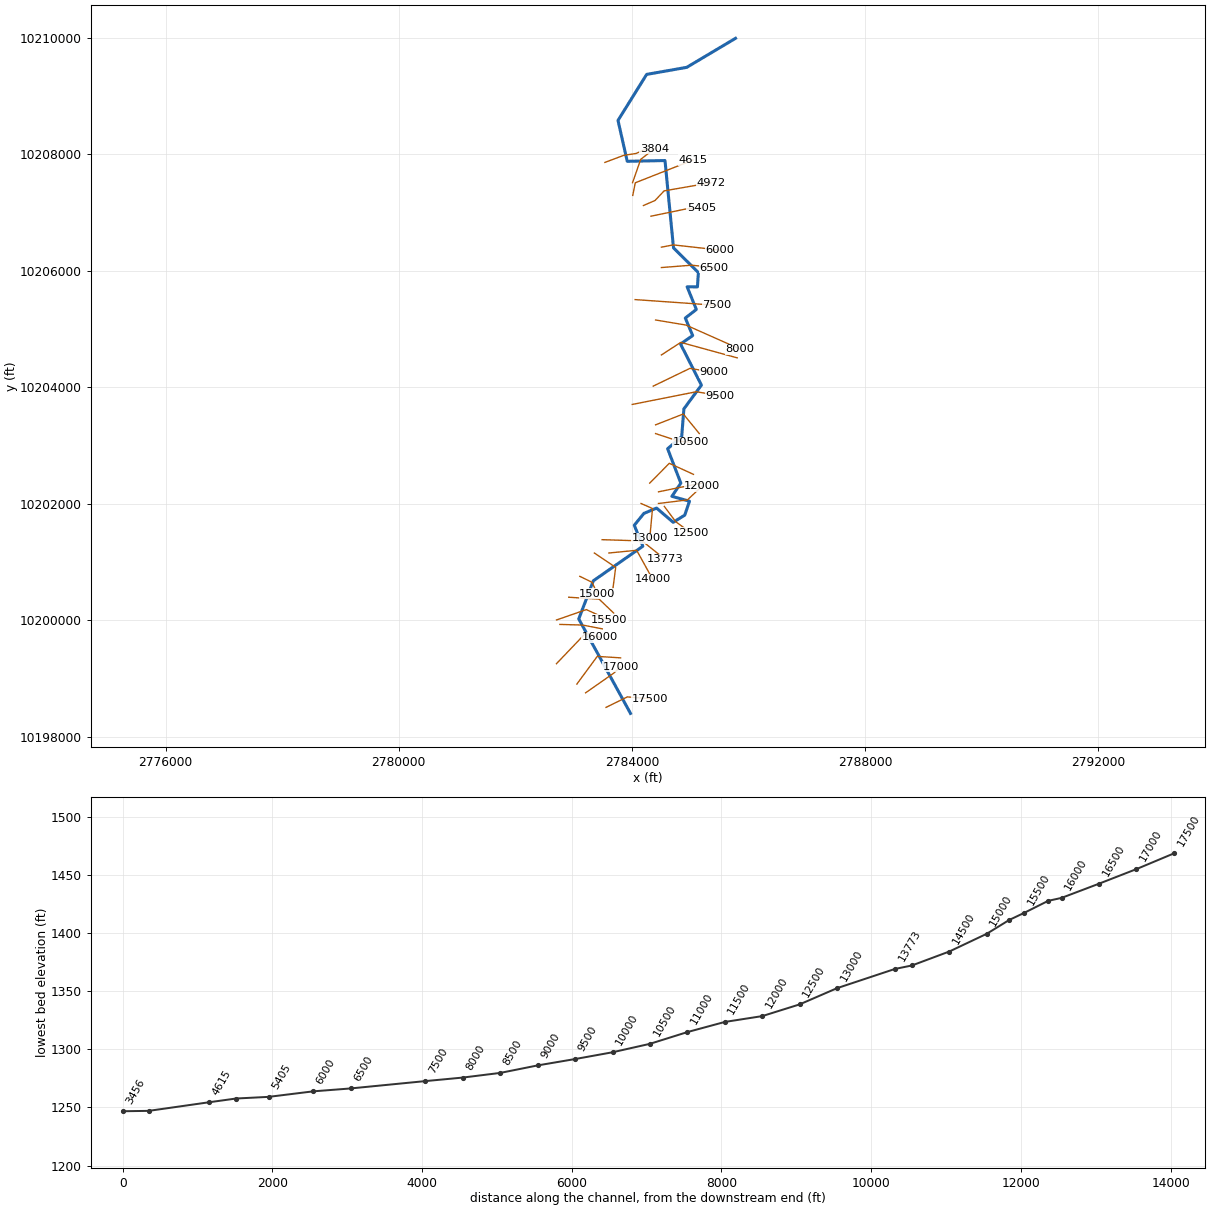
--- SANFERNANDO006.prj (project) ---

Proj Title=SANFERNANDO006 Base Level Engineering
Current Plan=p01
Default Exp/Contr=0.3,0.1
English Units
Geom File=g01
Flow File=f01
Plan File=p01
BEGIN DESCRIPTION:
SANFERNANDO006
END DESCRIPTION:

--- SANFERNANDO006.p01 (plan) ---

Plan Title=Multiple Run
Short Identifier=Multiple
Geom File=g01
Flow File=f01
Subcritical Flow
K Sum by GR= 0
Std Step Tol= 0.01
Critical Tol= 0.01
Num of Std Step Trials= 20
Max Error Tol= 0.3
Flow Tol Ratio= 0.001
Split Flow NTrial= 30
Split Flow Tol= 0.02
Split Flow Ratio= 0.02
Log Output Level= 0
Friction Slope Method= 1
Unsteady Friction Slope Method= 2
Unsteady Bridges Friction Slope Method= 1
Parabolic Critical Depth
Global Vel Dist=  1 , 1 , 1
Global Log Level= 0
CheckData=True
Encroach Param= -1, 0, 0, 0
BEGIN DESCRIPTION:
Multiple Run
END DESCRIPTION:

--- SANFERNANDO006.f01 (steady flow) ---

Flow Title=Multiple
Number of Profiles=7
Profile Names=10-year,25-year,50-year,1pct_min,100-year,1pct_plu,500-year
River Rch & RM= SANFERNANDO006,Reach-1,17500
     559     929    1499     981    2076    4394    2962
River Rch & RM= SANFERNANDO006,Reach-1,2500
     811    1374    2398    1543    3372    7371    4794
River Rch & RM= SANFERNANDO006,Reach-1,174
    1806    3190    5650    4380    8071   14873   11182
Boundary for River Rch & Prof#=SANFERNANDO006,Reach-1,1
Up Type=0
Dn Type=3
Dn Slope=0.005
Boundary for River Rch & Prof#=SANFERNANDO006,Reach-1,2
Up Type=0
Dn Type=3
Dn Slope=0.005
Boundary for River Rch & Prof#=SANFERNANDO006,Reach-1,3
Up Type=0
Dn Type=3
Dn Slope=0.005
Boundary for River Rch & Prof#=SANFERNANDO006,Reach-1,4
Up Type=0
Dn Type=3
Dn Slope=0.005
Boundary for River Rch & Prof#=SANFERNANDO006,Reach-1,5
Up Type=0
Dn Type=3
Dn Slope=0.005
Boundary for River Rch & Prof#=SANFERNANDO006,Reach-1,6
Up Type=0
Dn Type=3
Dn Slope=0.005
Boundary for River Rch & Prof#=SANFERNANDO006,Reach-1,7
Up Type=0
Dn Type=3
Dn Slope=0.005

--- SANFERNANDO006.g01 (geometry) ---

Geom Title=Existing Conditions

River Reach=SANFERNANDO006,Reach-1
Reach XY= 30
      2783975.25     10198400.00      2783088.00     10200021.00
      2783337.00     10200675.00      2784187.25     10201269.00
      2784040.25     10201629.00      2784205.75     10201833.00
      2784422.50     10201924.00      2784708.00     10201680.00
      2784906.25     10201803.00      2784987.00     10202042.00
      2784685.75     10202126.00      2784838.75     10202352.00
      2784612.50     10202943.00      2784853.75     10203152.00
      2784891.25     10203627.00      2785192.00     10204035.00
      2784834.00     10204740.00      2785042.25     10204886.00
      2784915.25     10205186.00      2785104.75     10205334.00
      2784946.50     10205723.00      2785123.50     10205721.00
      2785140.25     10205967.00      2784713.25     10206390.00
      2784567.25     10207890.00      2783919.50     10207877.00
      2783761.00     10208579.00      2784252.75     10209369.00
      2784940.25     10209490.00      2785776.75     10209988.00

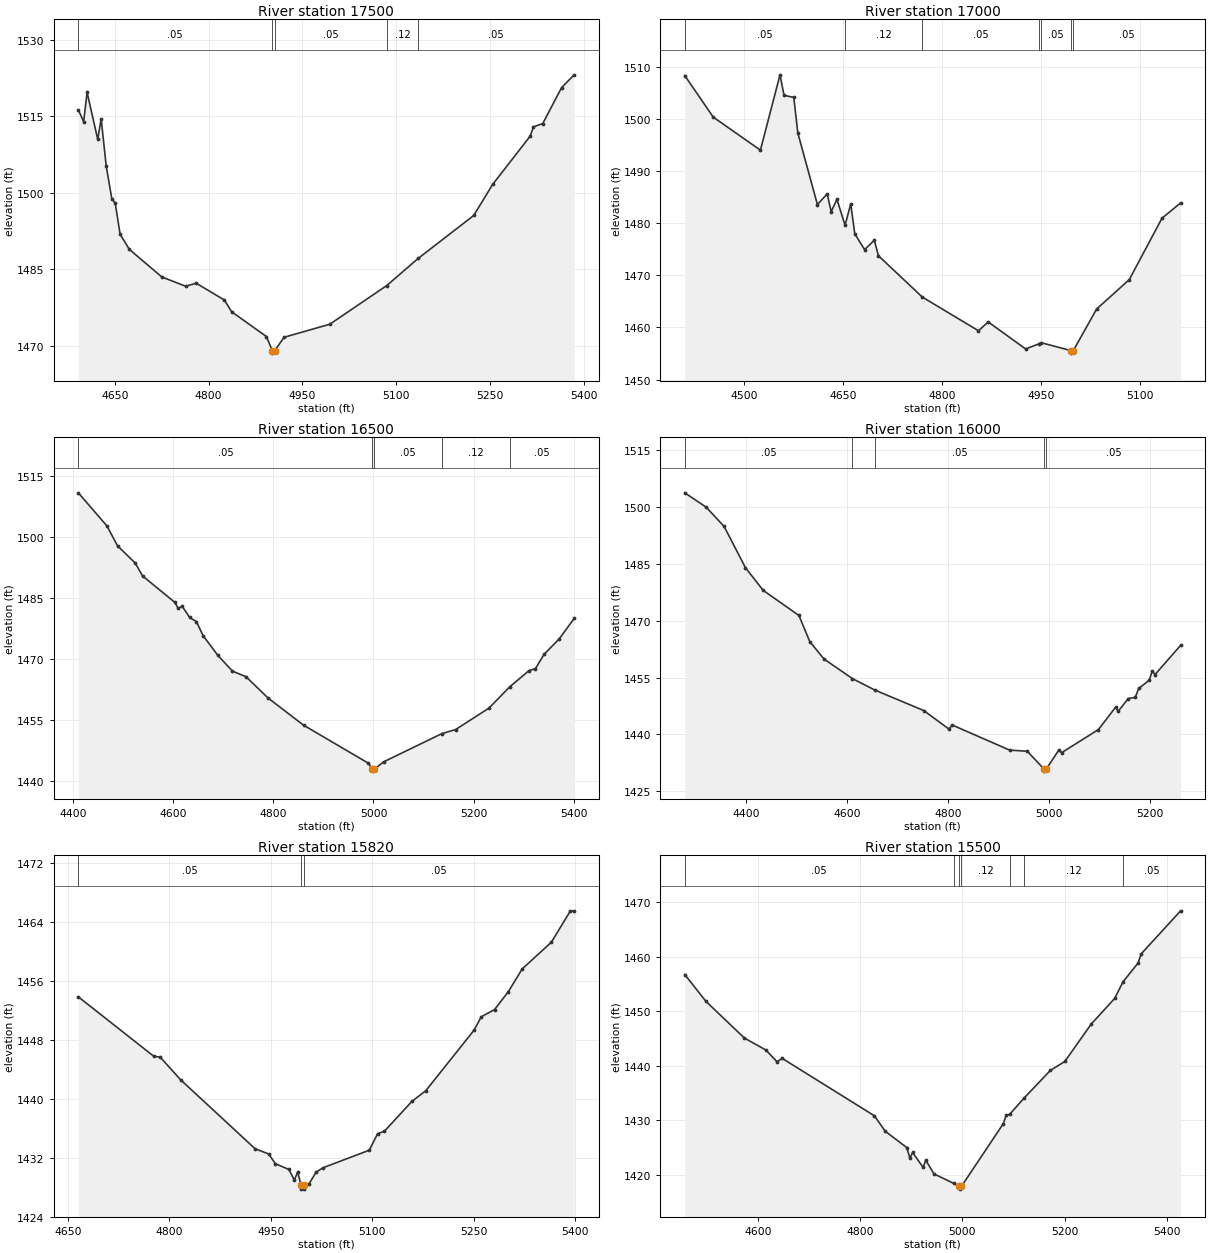
Type RM Length L Ch R = 1,17500,500,500,500
BEGIN DESCRIPTION:
SANFERNANDO006 34.0
END DESCRIPTION:
XS GIS Cut Line= 3
      2783555.68     10198503.11      2783922.23     10198682.73
      2784305.69     10198653.11
#Sta/Elev= 30
  4591.8 1516.29  4600.3 1513.96  4605.8 1519.73  4622.8 1510.51  4628.3 1514.51
  4636.4 1505.26  4645.3 1498.88  4650.8 1497.97  4658.6 1491.89  4673.3 1488.93
  4725.4 1483.50  4763.3 1481.70  4780.3 1482.28  4825.3 1478.99  4836.8 1476.70
  4892.5 1471.83  4901.9 1469.07  4902.1 1468.57  4905.9 1469.07  4920.8 1471.68
  4993.9 1474.24  5084.9 1481.82  5135.2 1487.15  5224.1 1495.58  5254.2 1501.65
  5314.4 1511.15  5319.5 1512.96  5334.4 1513.60  5364.5 1520.65  5384.6 1523.16
#Mann=5,-1,0
  4591.8    0.05       0  4901.9    0.05       0  4905.9    0.05       0
  5084.9    0.12       0  5135.2    0.05       0
Bank Sta=4901.9,4905.9
Exp/Cntr=0.3,0.1

Type RM Length L Ch R = 1,17000,500,500,500
BEGIN DESCRIPTION:
SANFERNANDO006 33.0
END DESCRIPTION:
XS GIS Cut Line= 3
      2783205.71     10198753.13      2783688.63     10199091.03
      2783805.71     10199203.14
#Sta/Elev= 30
  4410.6 1508.31  4453.7 1500.35  4525.2 1494.01  4554.9 1508.46  4561.0 1504.53
  4575.8 1504.13  4581.9 1497.31  4611.6 1483.58  4626.4 1485.63  4632.5 1482.21
  4641.2 1484.58  4653.5 1479.60  4662.1 1483.72  4668.2 1477.98  4683.1 1474.94
  4697.9 1476.73  4704.0 1473.77  4770.5 1465.84  4855.7 1459.37  4870.5 1461.06
  4927.2 1455.88  4947.9 1456.89  4951.0 1457.07  4995.5 1455.58  4995.7 1455.08
  4999.5 1455.58  5034.8 1463.54  5084.2 1469.17  5133.9 1480.96  5162.1 1483.89
#Mann=7,-1,0
  4410.6    0.05       0  4653.5    0.12       0  4770.5    0.05       0
  4947.9    0.12       0  4951.0    0.05       0  4995.5    0.05       0
  4999.5    0.05       0
Bank Sta=4995.5,4999.5
Exp/Cntr=0.3,0.1

Type RM Length L Ch R = 1,16500,500,500,500
BEGIN DESCRIPTION:
SANFERNANDO006 32.0
END DESCRIPTION:
XS GIS Cut Line= 3
      2783055.71     10198903.14      2783405.37     10199378.36
      2783805.68     10199353.11
#Sta/Elev= 30
  4410.0 1510.97  4467.4 1502.79  4488.3 1497.94  4523.8 1493.69  4538.4 1490.53
  4603.2 1484.00  4609.4 1482.58  4617.8 1483.03  4632.5 1480.31  4645.9 1479.30
  4659.5 1475.83  4688.8 1471.00  4718.1 1467.11  4745.2 1465.74  4789.1 1460.52
  4860.1 1453.83  4989.7 1444.47  4997.8 1443.02  4998.1 1442.52  5001.8 1443.02
  5020.4 1444.81  5136.2 1451.72  5164.2 1452.75  5230.8 1458.02  5272.5 1463.27
  5310.9 1467.25  5323.8 1467.74  5341.0 1471.25  5371.0 1475.01  5401.1 1480.07
#Mann=5,-1,0
  4410.0    0.05       0  4997.8    0.05       0  5001.8    0.05       0
  5136.2    0.12       0  5272.5    0.05       0
Bank Sta=4997.8,5001.8
Exp/Cntr=0.3,0.1

Type RM Length L Ch R = 1,16000,180,180,180
BEGIN DESCRIPTION:
SANFERNANDO006 31.0
END DESCRIPTION:
XS GIS Cut Line= 3
      2782705.68     10199253.10      2783203.88     10199774.56
      2783455.64     10199703.12
#Sta/Elev= 30
  4278.8 1503.80  4321.1 1500.02  4356.7 1494.93  4399.1 1484.02  4434.3 1478.03
  4505.1 1471.41  4526.5 1464.52  4554.8 1459.91  4611.1 1454.74  4656.0 1451.69
  4752.6 1446.30  4802.3 1441.43  4809.2 1442.47  4922.5 1435.87  4957.7 1435.56
  4991.2 1430.81  4991.5 1430.31  4995.2 1430.81  5020.5 1435.93  5025.7 1435.17
  5098.8 1441.29  5132.7 1447.17  5137.9 1446.10  5157.8 1449.48  5171.8 1449.79
  5178.6 1452.13  5199.4 1454.31  5205.7 1456.77  5210.9 1455.80  5261.7 1463.53
#Mann=5,-1,0
  4278.8    0.05       0  4611.1    0.12       0  4656.0    0.05       0
  4991.2    0.05       0  4995.2    0.05       0
Bank Sta=4991.2,4995.2
Exp/Cntr=0.3,0.1

Type RM Length L Ch R = 1,15820,320,320,320
BEGIN DESCRIPTION:
Mapping XS 3506ff66
END DESCRIPTION:
XS GIS Cut Line= 3
      2782764.49     10199927.06      2783155.09     10199916.21
      2783491.10     10199851.18
#Sta/Elev= 30
  4665.3 1453.87  4776.5 1445.82  4786.5 1445.66  4816.6 1442.59  4926.6 1433.23
  4946.6 1432.52  4956.6 1431.20  4976.6 1430.41  4984.6 1428.98  4989.6 1430.07
  4994.6 1428.24  4994.9 1427.74  4998.4 1427.74  4998.6 1428.24  5006.6 1428.49
  5016.6 1430.02  5026.6 1430.63  5095.5 1433.03  5107.6 1435.26  5117.8 1435.61
  5158.5 1439.67  5178.9 1441.11  5250.2 1449.33  5261.0 1451.16  5280.7 1452.15
  5301.1 1454.59  5321.5 1457.67  5364.6 1461.29  5392.8 1465.56  5398.3 1465.53
#Mann=3,-1,0
  4665.3    0.05       0  4994.6    0.05       0  4998.6    0.05       0
Bank Sta=4994.6,4998.6
Exp/Cntr=0.3,0.1

Type RM Length L Ch R = 1,15500,200,200,200
BEGIN DESCRIPTION:
SANFERNANDO006 30.0
END DESCRIPTION:
XS GIS Cut Line= 3
      2782705.65     10200003.10      2783218.23     10200181.67
      2783605.67     10200003.12
#Sta/Elev= 30
  4457.2 1456.76  4498.6 1451.84  4573.7 1445.12  4616.1 1442.90  4637.3 1440.78
  4647.8 1441.38  4827.9 1430.86  4849.0 1428.03  4891.4 1425.02  4897.3 1423.06
  4902.6 1424.13  4923.1 1421.40  4928.4 1422.71  4944.4 1420.20  4982.7 1418.48
  4994.0 1417.91  4994.3 1417.41  4998.0 1417.91  5080.0 1429.43  5085.5 1430.93
  5092.3 1431.13  5120.9 1434.14  5171.8 1439.17  5200.3 1440.83  5251.7 1447.67
  5297.6 1452.38  5314.1 1455.45  5343.5 1458.88  5349.5 1460.56  5426.6 1468.45
#Mann=7,-1,0
  4457.2    0.05       0  4982.7    0.12       0  4994.0    0.07       0
  4998.0    0.12       0  5092.3    0.05       0  5120.9    0.12       0
  5314.1    0.05       0
Bank Sta=4994,4998
Exp/Cntr=0.3,0.1

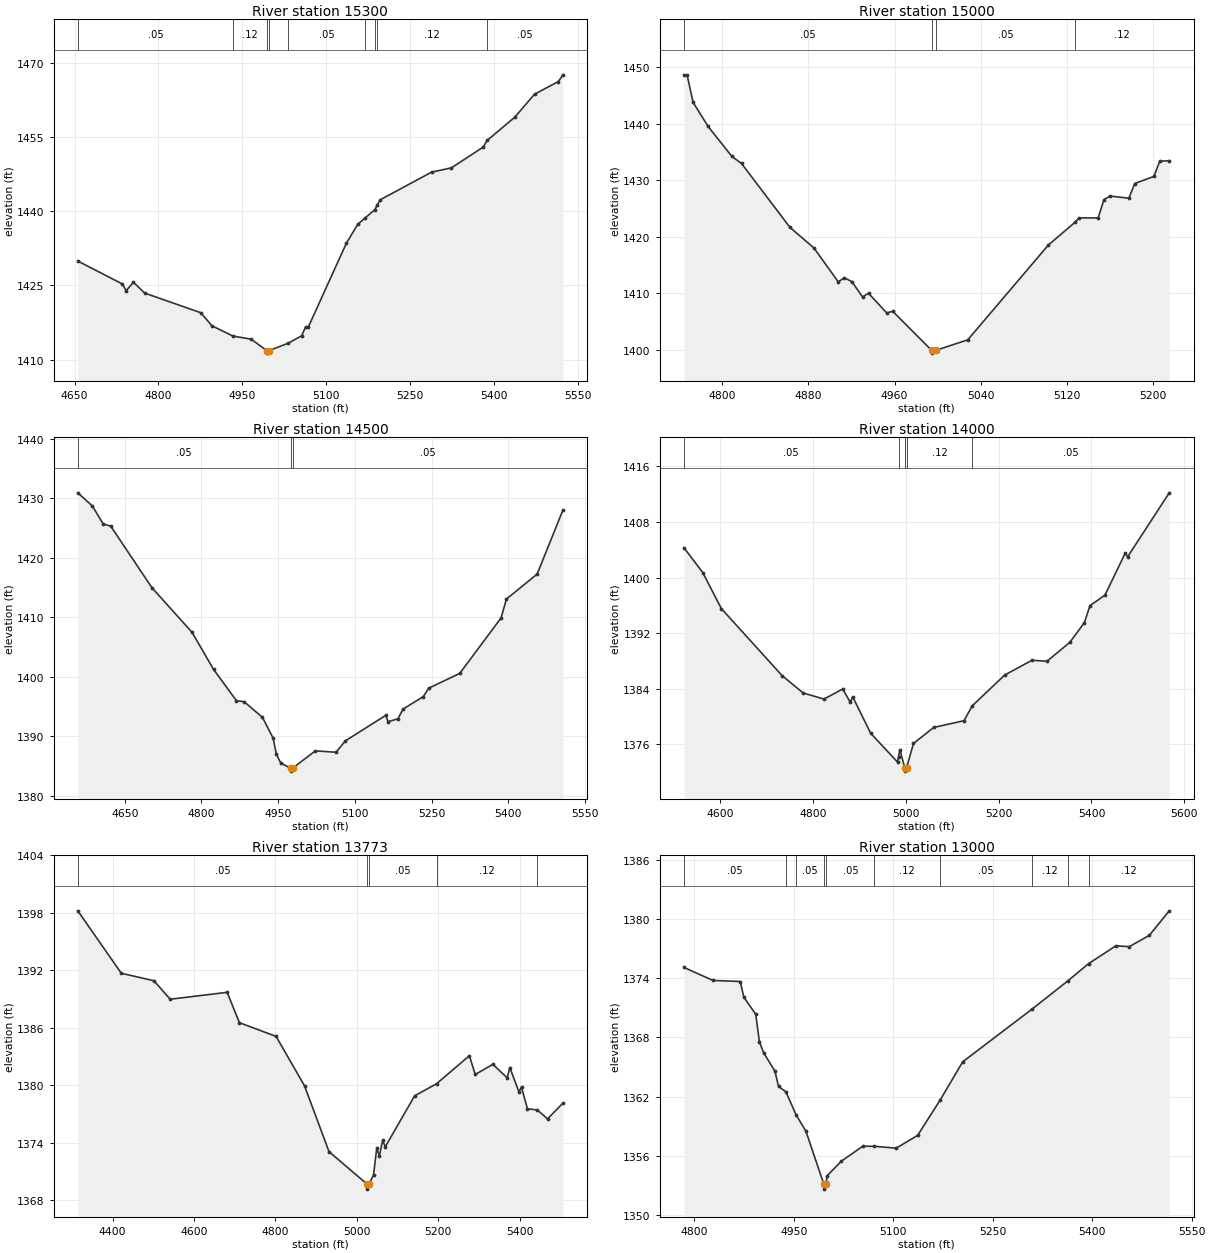
Type RM Length L Ch R = 1,15300,300,300,300
BEGIN DESCRIPTION:
Mapping XS c53fd129
END DESCRIPTION:
XS GIS Cut Line= 3
      2782916.41     10200393.64      2783437.21     10200361.09
      2783686.80     10200122.35
#Sta/Elev= 30
  4655.8 1429.91  4735.2 1425.29  4742.3 1423.93  4755.3 1425.62  4775.3 1423.44
  4875.5 1419.47  4895.5 1416.83  4933.1 1414.75  4965.7 1414.12  4993.7 1411.80
  4994.0 1411.30  4997.7 1411.80  5032.3 1413.33  5055.9 1414.81  5062.9 1416.58
  5068.0 1416.62  5136.0 1433.55  5156.0 1437.31  5169.3 1438.61  5186.5 1440.28
  5190.7 1441.14  5196.3 1442.29  5288.2 1447.89  5323.7 1448.75  5380.3 1452.94
  5387.4 1454.28  5436.9 1458.99  5472.1 1463.63  5514.6 1466.18  5523.0 1467.55
#Mann=9,-1,0
  4655.8    0.05       0  4933.1    0.12       0  4993.7    0.07       0
  4997.7    0.12       0  5032.3    0.05       0  5169.3    0.12       0
  5186.5    0.05       0  5190.7    0.12       0  5387.4    0.05       0
Bank Sta=4993.7,4997.7
Exp/Cntr=0.3,0.1

Type RM Length L Ch R = 1,15000,500,500,500
BEGIN DESCRIPTION:
SANFERNANDO006 29.0
END DESCRIPTION:
XS GIS Cut Line= 3
      2783105.70     10200753.10      2783317.17     10200649.24
      2783405.70     10200453.09
#Sta/Elev= 30
  4764.4 1448.64  4767.2 1448.64  4772.8 1443.78  4786.7 1439.52  4808.9 1434.20
  4817.8 1432.96  4862.8 1421.66  4885.2 1417.99  4907.7 1412.02  4913.3 1412.75
  4920.4 1412.06  4930.2 1409.36  4935.8 1410.00  4952.7 1406.53  4958.3 1406.81
  4994.4 1399.92  4994.6 1399.42  4998.4 1399.92  5028.0 1401.77  5102.9 1418.54
  5127.7 1422.57  5131.5 1423.34  5149.1 1423.33  5154.6 1426.58  5160.3 1427.20
  5177.7 1426.82  5183.2 1429.42  5200.9 1430.67  5206.4 1433.36  5215.2 1433.45
#Mann=4,-1,0
  4764.4    0.05       0  4994.4    0.05       0  4998.4    0.05       0
  5127.7    0.12       0
Bank Sta=4994.4,4998.4
Exp/Cntr=0.3,0.1

Type RM Length L Ch R = 1,14500,500,500,500
BEGIN DESCRIPTION:
SANFERNANDO006 28.0
END DESCRIPTION:
XS GIS Cut Line= 3
      2783355.65     10201153.14      2783721.70     10200905.76
      2783655.68     10200403.07
#Sta/Elev= 30
  4558.2 1430.94  4586.7 1428.73  4607.7 1425.72  4622.7 1425.33  4703.1 1415.00
  4781.5 1407.51  4823.8 1401.25  4868.4 1396.01  4883.4 1395.84  4919.3 1393.21
  4940.3 1389.69  4946.4 1387.02  4955.3 1385.50  4974.3 1384.67  4974.5 1384.17
  4978.3 1384.67  5022.8 1387.58  5063.2 1387.34  5081.4 1389.26  5160.2 1393.53
  5165.2 1392.49  5184.2 1392.96  5194.3 1394.60  5233.9 1396.70  5244.7 1398.12
  5305.2 1400.60  5385.9 1409.92  5396.4 1413.09  5456.5 1417.29  5507.0 1428.07
#Mann=3,-1,0
  4558.2    0.05       0  4974.3    0.05       0  4978.3    0.05       0
Bank Sta=4974.3,4978.3
Exp/Cntr=0.3,0.1

Type RM Length L Ch R = 1,14000,227,227,227
BEGIN DESCRIPTION:
SANFERNANDO006 27.0
END DESCRIPTION:
XS GIS Cut Line= 3
      2783605.71     10201153.11      2784080.84     10201199.58
      2784355.70     10200703.08
#Sta/Elev= 30
  4522.6 1404.29  4562.8 1400.74  4603.0 1395.54  4733.6 1385.91  4779.1 1383.40
  4824.0 1382.52  4864.2 1383.97  4880.7 1382.04  4885.7 1382.86  4924.5 1377.60
  4982.3 1373.46  4984.5 1374.25  4987.3 1375.25  4997.9 1372.65  4998.2 1372.15
  5001.9 1372.65  5016.7 1376.13  5060.2 1378.44  5125.5 1379.41  5143.4 1381.56
  5213.1 1385.98  5272.0 1388.11  5304.1 1387.96  5353.3 1390.68  5384.6 1393.51
  5396.9 1395.98  5428.9 1397.47  5472.4 1403.48  5478.2 1403.03  5567.5 1412.21
#Mann=5,-1,0
  4522.6    0.05       0  4984.5    0.12       0  4997.9    0.07       0
  5001.9    0.12       0  5143.4    0.05       0
Bank Sta=4997.9,5001.9
Exp/Cntr=0.3,0.1

Type RM Length L Ch R = 1,13773,773,773,773
BEGIN DESCRIPTION:
SANFERNANDO006 26.0
END DESCRIPTION:
XS GIS Cut Line= 3
      2783488.85     10201381.81      2784174.00     10201360.00
      2784570.34     10201044.63
#Sta/Elev= 30
  4314.5 1398.22  4421.4 1391.70  4501.4 1390.92  4541.5 1388.99  4681.5 1389.71
  4711.5 1386.54  4801.6 1385.11  4871.6 1379.94  4931.6 1373.08  5025.7 1369.66
  5026.0 1369.16  5029.7 1369.66  5041.0 1370.63  5049.0 1373.45  5055.4 1372.64
  5063.5 1374.26  5069.9 1373.58  5142.0 1378.90  5196.1 1380.17  5276.5 1383.09
  5290.9 1381.13  5334.2 1382.19  5369.4 1380.78  5375.8 1381.86  5398.2 1379.32
  5404.6 1379.81  5419.0 1377.55  5443.3 1377.43  5468.7 1376.50  5506.5 1378.15
#Mann=5,-1,0
  4314.5    0.05       0  5025.7    0.05       0  5029.7    0.05       0
  5196.1    0.12       0  5443.3    0.05       0
Bank Sta=5025.7,5029.7
Exp/Cntr=0.3,0.1

Type RM Length L Ch R = 1,13000,500,500,500
BEGIN DESCRIPTION:
SANFERNANDO006 25.0
END DESCRIPTION:
XS GIS Cut Line= 3
      2784155.70     10202003.11      2784352.98     10201917.13
      2784305.68     10201403.10
#Sta/Elev= 30
  4784.8 1375.08  4828.4 1373.77  4869.5 1373.66  4874.9 1372.07  4892.9 1370.34
  4898.4 1367.55  4904.8 1366.44  4921.8 1364.58  4927.2 1363.03  4938.3 1362.49
  4953.6 1360.17  4968.6 1358.48  4995.5 1353.13  4995.8 1352.63  4999.5 1353.13
  5000.0 1353.95  5022.1 1355.47  5054.2 1356.97  5071.8 1356.97  5104.5 1356.78
  5136.9 1358.07  5170.9 1361.66  5204.9 1365.53  5309.9 1370.89  5363.8 1373.75
  5394.6 1375.47  5435.8 1377.28  5455.9 1377.19  5486.1 1378.33  5516.2 1380.82
#Mann=10,-1,0
  4784.8    0.05       0  4938.3    0.12       0  4953.6    0.05       0
  4995.5    0.05       0  4999.5    0.05       0  5071.8    0.12       0
  5170.9    0.05       0  5309.9    0.12       0  5363.8    0.05       0
  5394.6    0.12       0
Bank Sta=4995.5,4999.5
Exp/Cntr=0.3,0.1

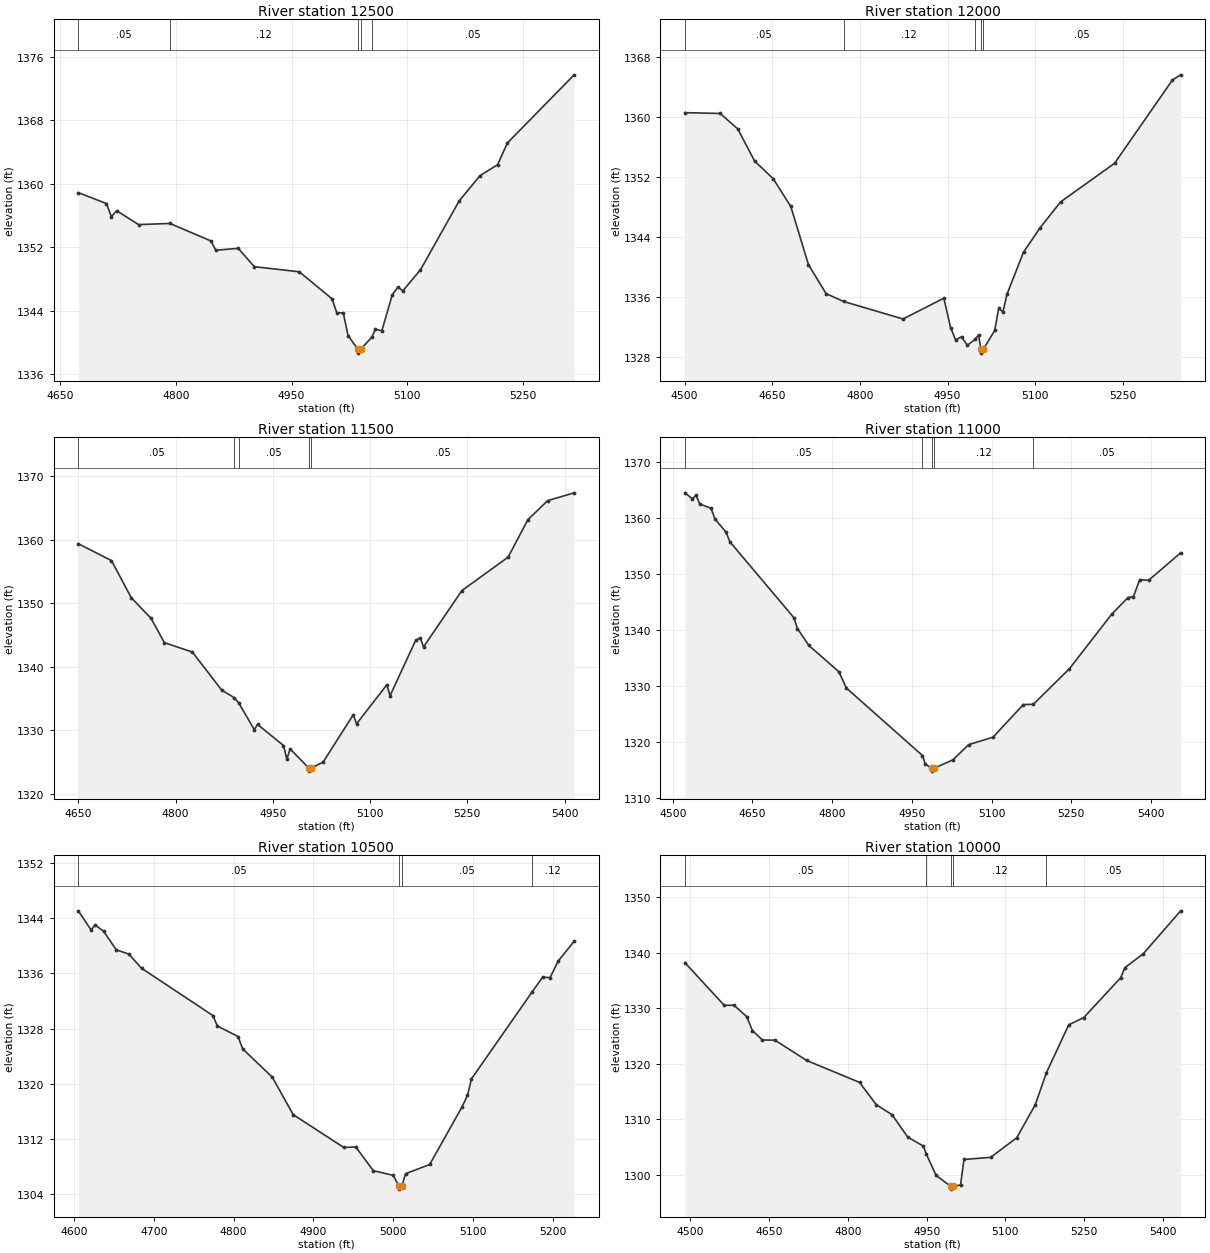
Type RM Length L Ch R = 1,12500,500,500,500
BEGIN DESCRIPTION:
SANFERNANDO006 24.0
END DESCRIPTION:
XS GIS Cut Line= 3
      2784555.67     10201953.13      2784750.73     10201691.05
      2785005.65     10201503.13
#Sta/Elev= 30
  4673.3 1358.87  4709.8 1357.50  4716.1 1355.86  4723.2 1356.59  4751.5 1354.85
  4792.2 1354.99  4845.4 1352.79  4851.6 1351.62  4880.8 1351.86  4901.7 1349.55
  4960.0 1348.91  5002.5 1345.51  5008.7 1343.75  5017.1 1343.73  5023.3 1340.88
  5035.9 1339.17  5036.2 1338.67  5039.9 1339.17  5054.1 1340.68  5058.8 1341.68
  5067.2 1341.49  5080.7 1346.02  5088.1 1347.00  5094.3 1346.50  5117.3 1349.16
  5167.5 1357.83  5194.5 1361.01  5217.4 1362.39  5230.0 1365.12  5316.7 1373.70
#Mann=5,-1,0
  4673.3    0.05       0  4792.2    0.12       0  5035.9    0.07       0
  5039.9    0.12       0  5054.1    0.05       0
Bank Sta=5035.9,5039.9
Exp/Cntr=0.3,0.1

Type RM Length L Ch R = 1,12000,500,500,500
BEGIN DESCRIPTION:
SANFERNANDO006 23.0
END DESCRIPTION:
XS GIS Cut Line= 3
      2784455.66     10202003.11      2784951.63     10202064.01
      2785205.70     10202303.13
#Sta/Elev= 30
  4500.3 1360.62  4560.8 1360.51  4591.0 1358.45  4619.8 1354.17  4651.5 1351.83
  4681.7 1348.12  4711.9 1340.38  4742.1 1336.51  4772.1 1335.46  4873.8 1333.13
  4943.6 1335.90  4955.2 1331.99  4963.8 1330.34  4973.9 1330.76  4983.9 1329.62
  4997.2 1330.43  5003.0 1330.99  5007.2 1329.08  5007.5 1328.58  5011.2 1329.08
  5030.7 1331.60  5037.5 1334.54  5044.8 1334.07  5051.7 1336.42  5080.0 1342.03
  5108.3 1345.27  5143.5 1348.73  5235.8 1353.87  5334.9 1364.97  5348.9 1365.66
#Mann=5,-1,0
  4500.3    0.05       0  4772.1    0.12       0  4997.2    0.05       0
  5007.2    0.05       0  5011.2    0.05       0
Bank Sta=5007.2,5011.2
Exp/Cntr=0.3,0.1

Type RM Length L Ch R = 1,11500,500,500,500
BEGIN DESCRIPTION:
SANFERNANDO006 22.0
END DESCRIPTION:
XS GIS Cut Line= 3
      2784455.68     10202203.11      2784798.56     10202273.86
      2785205.71     10202353.12
#Sta/Elev= 30
  4649.9 1359.34  4701.0 1356.69  4731.6 1350.84  4762.2 1347.59  4782.6 1343.78
  4825.9 1342.29  4871.0 1336.32  4890.8 1335.09  4897.2 1334.32  4921.3 1330.10
  4926.4 1330.91  4966.4 1327.59  4971.6 1325.46  4976.7 1327.05  5005.3 1324.06
  5005.5 1323.56  5009.3 1324.06  5027.6 1324.99  5074.0 1332.43  5079.1 1331.00
  5125.7 1337.13  5130.8 1335.44  5170.3 1344.14  5177.3 1344.55  5182.4 1343.10
  5241.6 1351.97  5312.9 1357.23  5343.5 1363.14  5374.0 1366.12  5414.8 1367.35
#Mann=5,-1,0
  4649.9    0.05       0  4890.8    0.12       0  4897.2    0.05       0
  5005.3    0.05       0  5009.3    0.05       0
Bank Sta=5005.3,5009.3
Exp/Cntr=0.3,0.1

Type RM Length L Ch R = 1,11000,500,500,500
BEGIN DESCRIPTION:
SANFERNANDO006 21.0
END DESCRIPTION:
XS GIS Cut Line= 3
      2784305.66     10202353.09      2784641.06     10202692.69
      2785055.68     10202503.11
#Sta/Elev= 30
  4522.7 1364.54  4536.8 1363.48  4543.9 1364.09  4551.0 1362.54  4572.2 1361.78
  4579.3 1359.89  4600.5 1357.50  4607.5 1355.80  4727.8 1342.27  4734.8 1340.29
  4756.1 1337.29  4812.7 1332.59  4826.8 1329.68  4970.0 1317.63  4975.3 1316.11
  4987.4 1315.34  4987.7 1314.84  4991.4 1315.34  5027.1 1316.84  5056.8 1319.56
  5102.9 1320.91  5159.9 1326.73  5178.6 1326.77  5246.5 1333.12  5326.5 1342.90
  5356.9 1345.84  5367.1 1346.01  5378.9 1349.04  5395.6 1348.91  5455.9 1353.82
#Mann=5,-1,0
  4522.7    0.05       0  4970.0    0.12       0  4987.4    0.07       0
  4991.4    0.12       0  5178.6    0.05       0
Bank Sta=4987.4,4991.4
Exp/Cntr=0.3,0.1

Type RM Length L Ch R = 1,10500,500,500,500
BEGIN DESCRIPTION:
SANFERNANDO006 20.0
END DESCRIPTION:
XS GIS Cut Line= 3
      2784405.66     10203203.12      2784780.22     10203078.97
      2785005.64     10203053.12
#Sta/Elev= 30
  4605.4 1345.04  4621.3 1342.28  4626.5 1343.00  4637.0 1342.09  4653.0 1339.39
  4668.6 1338.78  4684.7 1336.72  4774.0 1329.88  4779.8 1328.35  4805.6 1326.84
  4811.4 1325.05  4848.4 1320.97  4874.8 1315.52  4938.2 1310.77  4953.1 1310.85
  4975.2 1307.41  5000.0 1306.74  5007.1 1305.24  5007.3 1304.74  5011.1 1305.24
  5015.6 1306.97  5045.8 1308.31  5086.0 1316.57  5093.2 1318.31  5098.2 1320.71
  5173.8 1333.23  5187.4 1335.43  5196.7 1335.37  5206.8 1337.75  5226.9 1340.64
#Mann=4,-1,0
  4605.4    0.05       0  5007.1    0.05       0  5011.1    0.05       0
  5173.8    0.12       0
Bank Sta=5007.1,5011.1
Exp/Cntr=0.3,0.1

Type RM Length L Ch R = 1,10000,500,500,500
BEGIN DESCRIPTION:
SANFERNANDO006 19.0
END DESCRIPTION:
XS GIS Cut Line= 3
      2784405.71     10203353.12      2784881.37     10203539.32
      2785155.67     10203203.13
#Sta/Elev= 30
  4489.2 1338.24  4564.3 1330.55  4582.8 1330.57  4607.3 1328.50  4618.0 1326.00
  4637.1 1324.31  4661.0 1324.28  4721.2 1320.63  4822.1 1316.68  4854.2 1312.65
  4884.0 1310.87  4913.9 1306.84  4943.7 1305.22  4949.2 1303.81  4968.1 1299.93
  4996.0 1297.97  4996.2 1297.47  5000.0 1297.97  5014.6 1298.21  5021.1 1302.81
  5072.0 1303.19  5121.6 1306.71  5156.8 1312.63  5178.2 1318.42  5220.7 1327.03
  5249.4 1328.35  5319.7 1335.51  5327.7 1337.32  5362.8 1339.83  5433.9 1347.55
#Mann=5,-1,0
  4489.2    0.05       0  4949.2    0.12       0  4996.0    0.07       0
  5000.0    0.12       0  5178.2    0.05       0
Bank Sta=4996,5000
Exp/Cntr=0.3,0.1

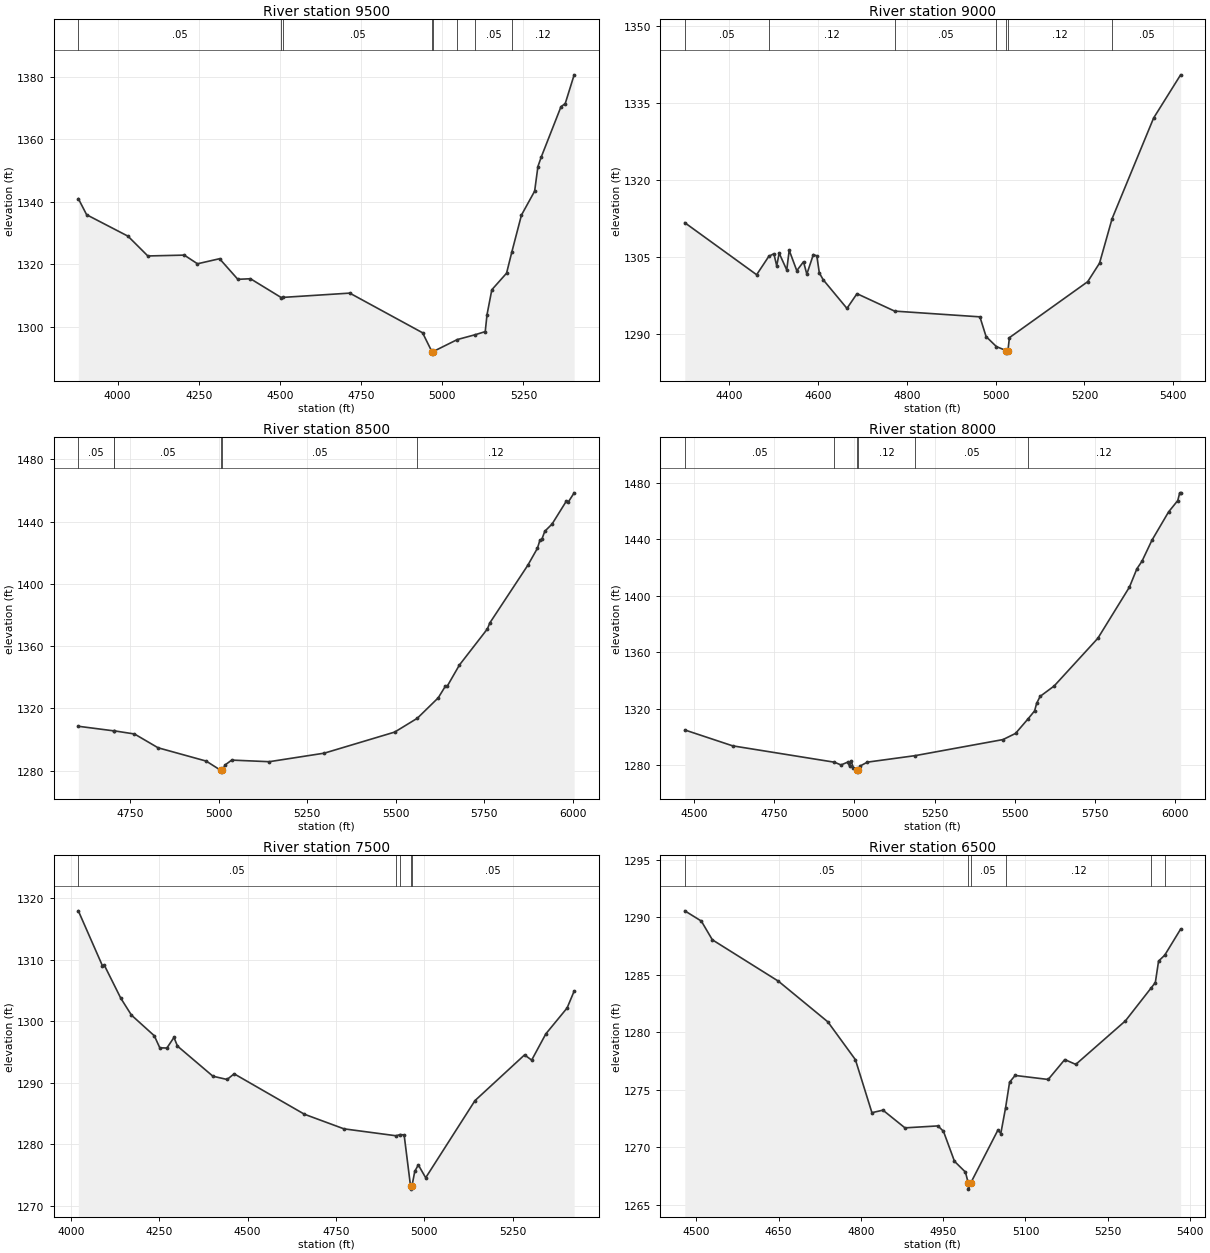
Type RM Length L Ch R = 1,9500,500,500,500
BEGIN DESCRIPTION:
SANFERNANDO006 18.0
END DESCRIPTION:
XS GIS Cut Line= 3
      2784005.66     10203703.11      2785105.22     10203921.30
      2785505.66     10203853.12
#Sta/Elev= 30
  3879.0 1341.04  3904.6 1335.89  4031.9 1329.04  4093.1 1322.71  4205.3 1322.98
  4246.0 1320.21  4314.0 1321.83  4370.3 1315.24  4409.2 1315.43  4503.8 1309.42
  4508.7 1309.46  4715.0 1310.83  4939.3 1298.15  4967.9 1292.14  4968.1 1291.64
  4971.9 1292.14  5046.3 1295.98  5100.1 1297.49  5132.3 1298.52  5137.8 1303.93
  5152.6 1311.90  5198.0 1317.20  5214.3 1324.01  5243.9 1335.79  5284.5 1343.44
  5294.6 1351.31  5304.8 1354.34  5365.6 1370.43  5378.7 1371.44  5406.2 1380.63
#Mann=8,-1,0
  3879.0    0.05       0  4503.8    0.12       0  4508.7    0.05       0
  4967.9    0.05       0  4971.9    0.05       0  5046.3    0.12       0
  5100.1    0.05       0  5214.3    0.12       0
Bank Sta=4967.9,4971.9
Exp/Cntr=0.3,0.1

Type RM Length L Ch R = 1,9000,500,500,500
BEGIN DESCRIPTION:
SANFERNANDO006 17.0
END DESCRIPTION:
XS GIS Cut Line= 3
      2784365.17     10204017.69      2784995.07     10204322.33
      2785405.68     10204253.11
#Sta/Elev= 30
  4300.3 1311.62  4462.0 1301.47  4489.5 1305.07  4500.8 1305.57  4507.2 1303.20
  4512.7 1305.68  4529.8 1302.40  4535.3 1306.25  4552.4 1302.26  4567.5 1304.00
  4575.0 1301.59  4589.7 1305.41  4597.5 1305.14  4603.1 1301.83  4611.9 1300.48
  4665.3 1294.90  4687.9 1297.77  4772.6 1294.37  4964.6 1293.25  4978.5 1289.40
  5001.8 1287.44  5023.7 1286.67  5023.9 1286.17  5027.7 1286.67  5031.0 1289.19
  5207.2 1300.11  5233.9 1303.73  5262.1 1312.40  5355.6 1332.05  5416.4 1340.48
#Mann=7,-1,0
  4300.3    0.05       0  4489.5    0.12       0  4772.6    0.05       0
  5001.8    0.12       0  5023.7    0.05       0  5027.7    0.12       0
  5262.1    0.05       0
Bank Sta=5023.7,5027.7
Exp/Cntr=0.3,0.1

Type RM Length L Ch R = 1,8500,500,500,500
BEGIN DESCRIPTION:
SANFERNANDO006 16.0
END DESCRIPTION:
XS GIS Cut Line= 3
      2784505.72     10204553.13      2784837.81     10204768.66
      2785805.65     10204503.12
#Sta/Elev= 30
  4604.1 1308.54  4703.9 1305.60  4704.5 1305.64  4762.6 1303.58  4829.1 1294.72
  4965.0 1286.16  5006.2 1280.21  5006.4 1279.71  5010.2 1280.21  5018.5 1283.71
  5037.0 1286.80  5143.0 1285.77  5298.5 1291.27  5497.1 1304.81  5561.0 1313.71
  5620.0 1326.83  5640.1 1334.30  5645.2 1334.24  5679.7 1347.90  5759.0 1371.19
  5765.1 1374.80  5872.7 1411.99  5899.9 1422.94  5907.1 1428.23  5912.3 1428.65
  5920.7 1433.85  5941.4 1438.56  5981.2 1453.12  5986.4 1452.45  6003.6 1458.57
#Mann=6,-1,0
  4604.1    0.05       0  4703.9    0.12       0  4704.5    0.05       0
  5006.2    0.05       0  5010.2    0.05       0  5561.0    0.12       0
Bank Sta=5006.2,5010.2
Exp/Cntr=0.3,0.1

Type RM Length L Ch R = 1,8000,500,500,500
BEGIN DESCRIPTION:
SANFERNANDO006 15.0
END DESCRIPTION:
XS GIS Cut Line= 3
      2784405.66     10205153.12      2784927.09     10205065.78
      2785855.72     10204653.09
#Sta/Elev= 30
  4471.3 1304.90  4620.5 1293.63  4937.4 1282.04  4958.0 1280.09  4978.3 1282.03
  4984.6 1279.32  4989.7 1282.62  4996.8 1278.13  5007.4 1276.21  5007.7 1275.71
  5011.4 1276.21  5016.9 1279.25  5040.1 1282.08  5188.8 1286.68  5462.8 1298.08
  5501.8 1302.44  5540.6 1312.70  5561.3 1318.45  5567.5 1323.73  5578.4 1328.69
  5622.2 1336.08  5758.3 1369.89  5856.8 1406.22  5880.0 1419.19  5895.8 1424.50
  5926.6 1439.30  5978.5 1459.41  6007.3 1467.53  6013.4 1473.00  6016.2 1473.00
#Mann=6,-1,0
  4471.3    0.05       0  4937.4    0.12       0  5007.4    0.07       0
  5011.4    0.12       0  5188.8    0.05       0  5540.6    0.12       0
Bank Sta=5007.4,5011.4
Exp/Cntr=0.3,0.1

Type RM Length L Ch R = 1,7500,1000,1000,1000
BEGIN DESCRIPTION:
SANFERNANDO006 14.0
END DESCRIPTION:
XS GIS Cut Line= 3
      2784055.64     10205503.11      2785032.44     10205434.67
      2785455.67     10205403.11
#Sta/Elev= 30
  4020.8 1317.95  4089.2 1308.99  4094.2 1309.12  4141.1 1303.72  4171.2 1300.98
  4235.9 1297.62  4251.4 1295.66  4271.5 1295.63  4291.5 1297.35  4301.5 1295.94
  4401.8 1291.04  4441.9 1290.51  4461.9 1291.43  4661.0 1284.85  4772.7 1282.48
  4920.5 1281.35  4931.6 1281.55  4943.1 1281.49  4961.2 1273.17  4961.4 1272.67
  4965.2 1273.17  4973.2 1275.56  4983.2 1276.62  5004.1 1274.52  5143.6 1287.07
  5284.0 1294.51  5304.1 1293.66  5344.2 1297.93  5404.4 1302.14  5424.4 1304.89
#Mann=5,-1,0
  4020.8    0.05       0  4920.5    0.12       0  4931.6    0.05       0
  4961.2    0.05       0  4965.2    0.05       0
Bank Sta=4961.2,4965.2
Exp/Cntr=0.3,0.1

Type RM Length L Ch R = 1,6500,500,500,500
BEGIN DESCRIPTION:
SANFERNANDO006 13.0
END DESCRIPTION:
XS GIS Cut Line= 3
      2784505.64     10206053.11      2785025.04     10206093.86
      2785405.66     10206053.11
#Sta/Elev= 30
  4479.0 1290.55  4509.1 1289.66  4529.2 1288.03  4649.6 1284.43  4739.8 1280.89
  4790.0 1277.60  4820.1 1272.99  4840.2 1273.21  4880.3 1271.67  4940.5 1271.84
  4950.5 1271.37  4970.6 1268.76  4990.6 1267.82  4995.8 1266.84  4996.1 1266.34
  4999.8 1266.84  5050.0 1271.50  5055.0 1271.17  5063.7 1273.41  5071.0 1275.64
  5081.1 1276.23  5141.4 1275.88  5171.6 1277.61  5191.7 1277.19  5282.2 1280.98
  5329.2 1283.85  5336.7 1284.31  5342.6 1286.18  5353.8 1286.69  5382.8 1288.96
#Mann=6,-1,0
  4479.0    0.05       0  4995.8    0.05       0  4999.8    0.05       0
  5063.7    0.12       0  5329.2    0.05       0  5353.8    0.12       0
Bank Sta=4995.8,4999.8
Exp/Cntr=0.3,0.1

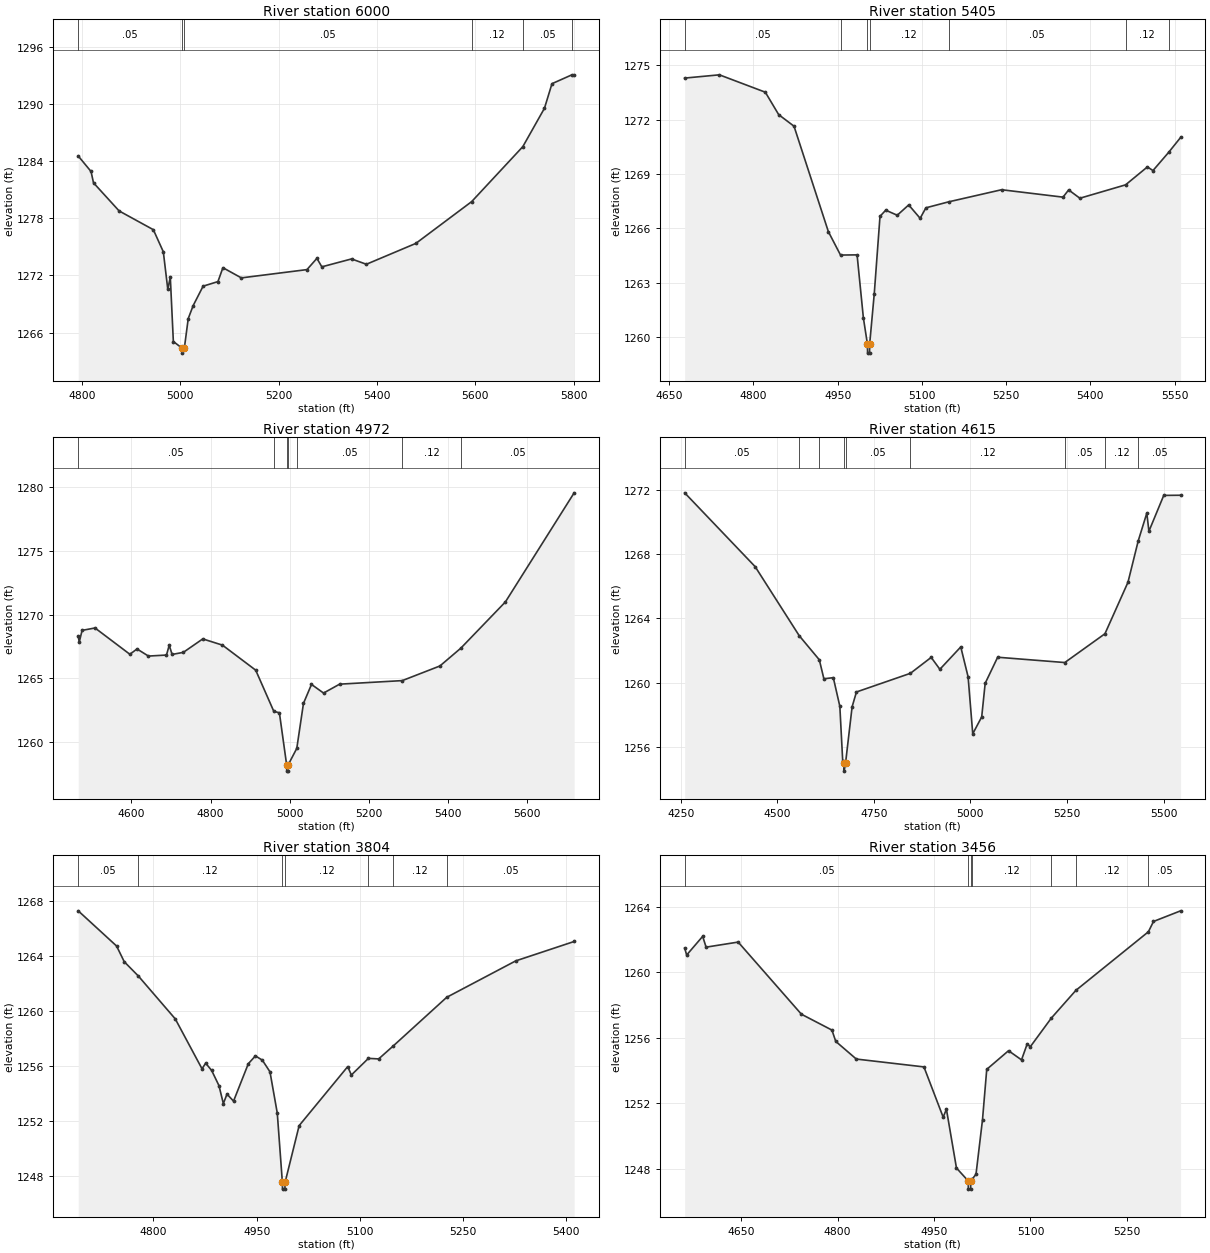
Type RM Length L Ch R = 1,6000,595,595,595
BEGIN DESCRIPTION:
SANFERNANDO006 12.0
END DESCRIPTION:
XS GIS Cut Line= 3
      2784505.65     10206403.11      2784709.65     10206442.16
      2785505.69     10206353.11
#Sta/Elev= 30
  4792.3 1284.54  4818.4 1282.91  4823.4 1281.72  4875.5 1278.77  4945.1 1276.80
  4965.4 1274.48  4974.5 1270.54  4979.6 1271.83  4985.8 1265.06  5004.1 1264.34
  5004.3 1263.84  5008.1 1264.34  5016.1 1267.47  5026.2 1268.84  5046.3 1270.87
  5076.5 1271.35  5086.6 1272.81  5124.1 1271.74  5257.6 1272.61  5277.8 1273.79
  5287.8 1272.90  5348.2 1273.73  5378.4 1273.17  5479.0 1275.36  5592.6 1279.75
  5696.6 1285.52  5740.6 1289.55  5755.9 1292.13  5796.4 1293.06  5801.0 1293.00
#Mann=6,-1,0
  4792.3    0.05       0  5004.1    0.05       0  5008.1    0.05       0
  5592.6    0.12       0  5696.6    0.05       0  5796.4    0.12       0
Bank Sta=5004.1,5008.1
Exp/Cntr=0.3,0.1

Type RM Length L Ch R = 1,5405,433,433,433
BEGIN DESCRIPTION:
Mapping XS 9cd7c617
END DESCRIPTION:
XS GIS Cut Line= 3
      2784325.04     10206934.59      2784940.55     10207061.71
      2785194.80     10207075.09
#Sta/Elev= 30
  4677.6 1274.30  4739.4 1274.48  4821.2 1273.52  4845.0 1272.28  4872.3 1271.64
  4933.5 1265.81  4955.1 1264.52  4984.6 1264.53  4995.8 1261.05  5003.0 1259.60
  5003.3 1259.10  5006.8 1259.10  5007.0 1259.60  5015.2 1262.39  5025.4 1266.66
  5035.6 1267.00  5056.1 1266.72  5076.5 1267.29  5096.9 1266.55  5107.1 1267.13
  5147.5 1267.46  5241.9 1268.13  5351.3 1267.72  5361.3 1268.12  5381.3 1267.66
  5462.7 1268.40  5501.5 1269.39  5511.5 1269.19  5539.5 1270.20  5560.7 1271.02
#Mann=7,-1,0
  4677.6    0.05       0  4955.1    0.12       0  5003.0    0.07       0
  5007.0    0.12       0  5147.5    0.05       0  5462.7    0.12       0
  5539.5    0.05       0
Bank Sta=5003,5007
Exp/Cntr=0.3,0.1

Type RM Length L Ch R = 1,4972,357,357,357
BEGIN DESCRIPTION:
Mapping XS 2444817a
END DESCRIPTION:
XS GIS Cut Line= 4
      2784196.72     10207117.74      2784396.38     10207204.55
      2784552.63     10207369.48      2785350.25     10207508.20
#Sta/Elev= 30
  4465.3 1268.31  4467.9 1267.83  4475.1 1268.76  4507.8 1268.95  4596.0 1266.88
  4614.0 1267.30  4642.9 1266.74  4688.6 1266.82  4695.5 1267.59  4702.8 1266.87
  4731.1 1267.03  4780.4 1268.09  4830.2 1267.60  4914.3 1265.63  4960.1 1262.39
  4974.2 1262.28  4992.5 1258.19  4992.8 1257.69  4996.3 1257.69  4996.5 1258.19
  5018.2 1259.48  5035.1 1263.02  5055.4 1264.51  5085.9 1263.83  5126.5 1264.53
  5285.0 1264.81  5380.2 1265.96  5433.1 1267.36  5545.9 1271.00  5719.8 1279.58
#Mann=7,-1,0
  4465.3    0.05       0  4960.1    0.12       0  4992.5    0.07       0
  4996.5    0.12       0  5018.2    0.05       0  5285.0    0.12       0
  5433.1    0.05       0
Bank Sta=4992.5,4996.5
Exp/Cntr=0.3,0.1

Type RM Length L Ch R = 1,4615,811,811,811
BEGIN DESCRIPTION:
Mapping XS 13f8be87
END DESCRIPTION:
XS GIS Cut Line= 3
      2784014.44     10207291.39      2784057.84     10207508.37
      2785046.34     10207898.57
#Sta/Elev= 30
  4260.2 1271.81  4442.7 1267.22  4556.7 1262.93  4608.8 1261.43  4620.6 1260.25
  4645.0 1260.32  4661.9 1258.54  4669.4 1255.11  4672.7 1255.01  4673.0 1254.51
  4676.7 1255.01  4693.7 1258.51  4704.9 1259.43  4844.6 1260.59  4898.4 1261.58
  4920.9 1260.84  4975.0 1262.23  4994.0 1260.37  5006.0 1256.83  5029.2 1257.88
  5038.2 1259.97  5070.5 1261.59  5244.3 1261.26  5348.3 1263.05  5407.9 1266.25
  5434.3 1268.81  5456.7 1270.55  5462.1 1269.42  5500.5 1271.65  5544.2 1271.66
#Mann=9,-1,0
  4260.2    0.05       0  4556.7    0.12       0  4608.8    0.05       0
  4672.7    0.07       0  4676.7    0.05       0  4844.6    0.12       0
  5244.3    0.05       0  5348.3    0.12       0  5434.3    0.05       0
Bank Sta=4672.7,4676.7
Exp/Cntr=0.3,0.1

Type RM Length L Ch R = 1,3804,348,348,348
BEGIN DESCRIPTION:
Mapping XS fd583590
END DESCRIPTION:
XS GIS Cut Line= 3
      2784010.64     10207509.98      2784151.12     10207911.36
      2784385.29     10208092.00
#Sta/Elev= 30
  4690.6 1267.30  4746.4 1264.74  4757.5 1263.60  4778.0 1262.56  4831.7 1259.44
  4870.6 1255.81  4875.9 1256.22  4884.6 1255.69  4895.2 1254.59  4901.6 1253.28
  4906.9 1253.97  4916.4 1253.46  4937.9 1256.18  4948.2 1256.75  4958.3 1256.44
  4969.4 1255.59  4980.0 1252.59  4987.4 1247.56  4987.6 1247.06  4991.1 1247.06
  4991.4 1247.56  5011.8 1251.68  5082.4 1255.97  5087.7 1255.36  5112.5 1256.57
  5127.4 1256.53  5148.3 1257.46  5226.3 1261.01  5326.7 1263.66  5411.6 1265.07
#Mann=7,-1,0
  4690.6    0.05       0  4778.0    0.12       0  4987.4    0.07       0
  4991.4    0.12       0  5112.5    0.05       0  5148.3    0.12       0
  5226.3    0.05       0
Bank Sta=4987.4,4991.4
Exp/Cntr=0.3,0.1

Type RM Length L Ch R = 1,3456,328,328,328
BEGIN DESCRIPTION:
Mapping XS 0f960766
END DESCRIPTION:
XS GIS Cut Line= 4
      2783535.67     10207857.85      2783856.75     10207978.26
      2784070.84     10208011.71      2784264.20     10208098.38
#Sta/Elev= 30
  4562.1 1261.47  4565.2 1261.05  4590.1 1262.19  4595.4 1261.53  4645.3 1261.84
  4743.7 1257.43  4791.2 1256.46  4797.1 1255.77  4829.1 1254.69  4934.3 1254.21
  4964.2 1251.14  4969.3 1251.62  4984.9 1248.03  5003.2 1247.24  5003.4 1246.74
  5006.9 1246.74  5007.2 1247.24  5009.2 1247.34  5015.3 1247.65  5025.4 1250.98
  5032.0 1254.06  5065.9 1255.20  5086.1 1254.64  5094.8 1255.60  5099.9 1255.45
  5132.4 1257.19  5170.7 1258.89  5283.5 1262.47  5291.4 1263.10  5333.6 1263.75
#Mann=7,-1,0
  4562.1    0.05       0  5003.2    0.03       0  5007.2    0.05       0
  5009.2    0.12       0  5132.4    0.05       0  5170.7    0.12       0
  5283.5    0.05       0
Bank Sta=5003.2,5007.2
Exp/Cntr=0.3,0.1