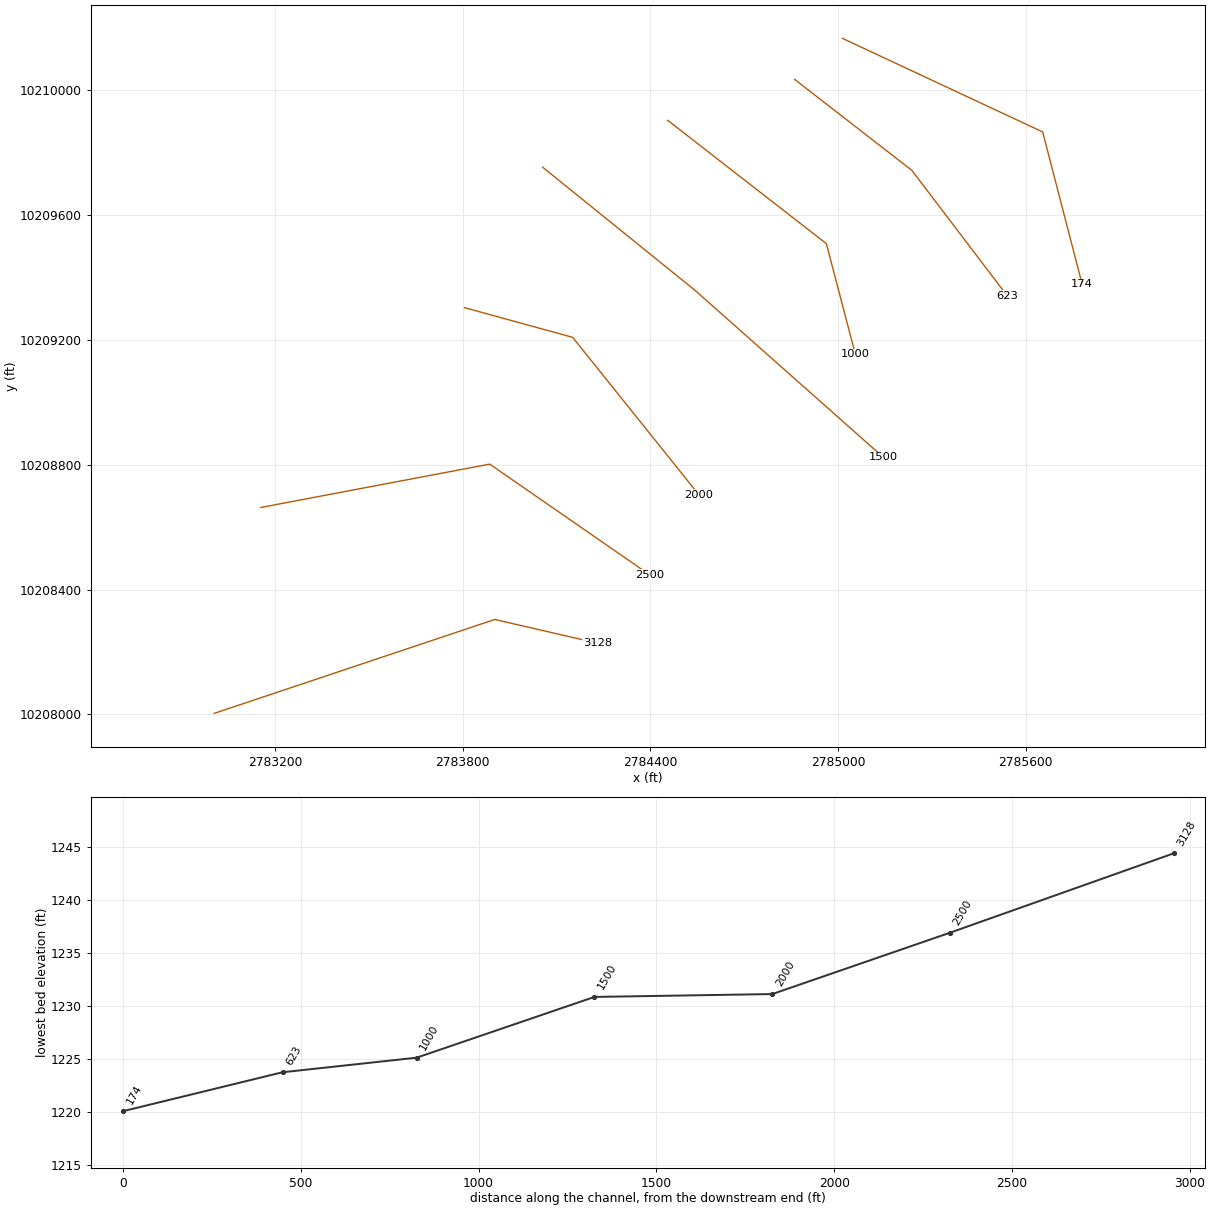
HEC-RAS study SANFERNANDO006.prj: SANFERNANDO006 Base Level Engineering

--- SANFERNANDO006.g01 (geometry) --- (continued)

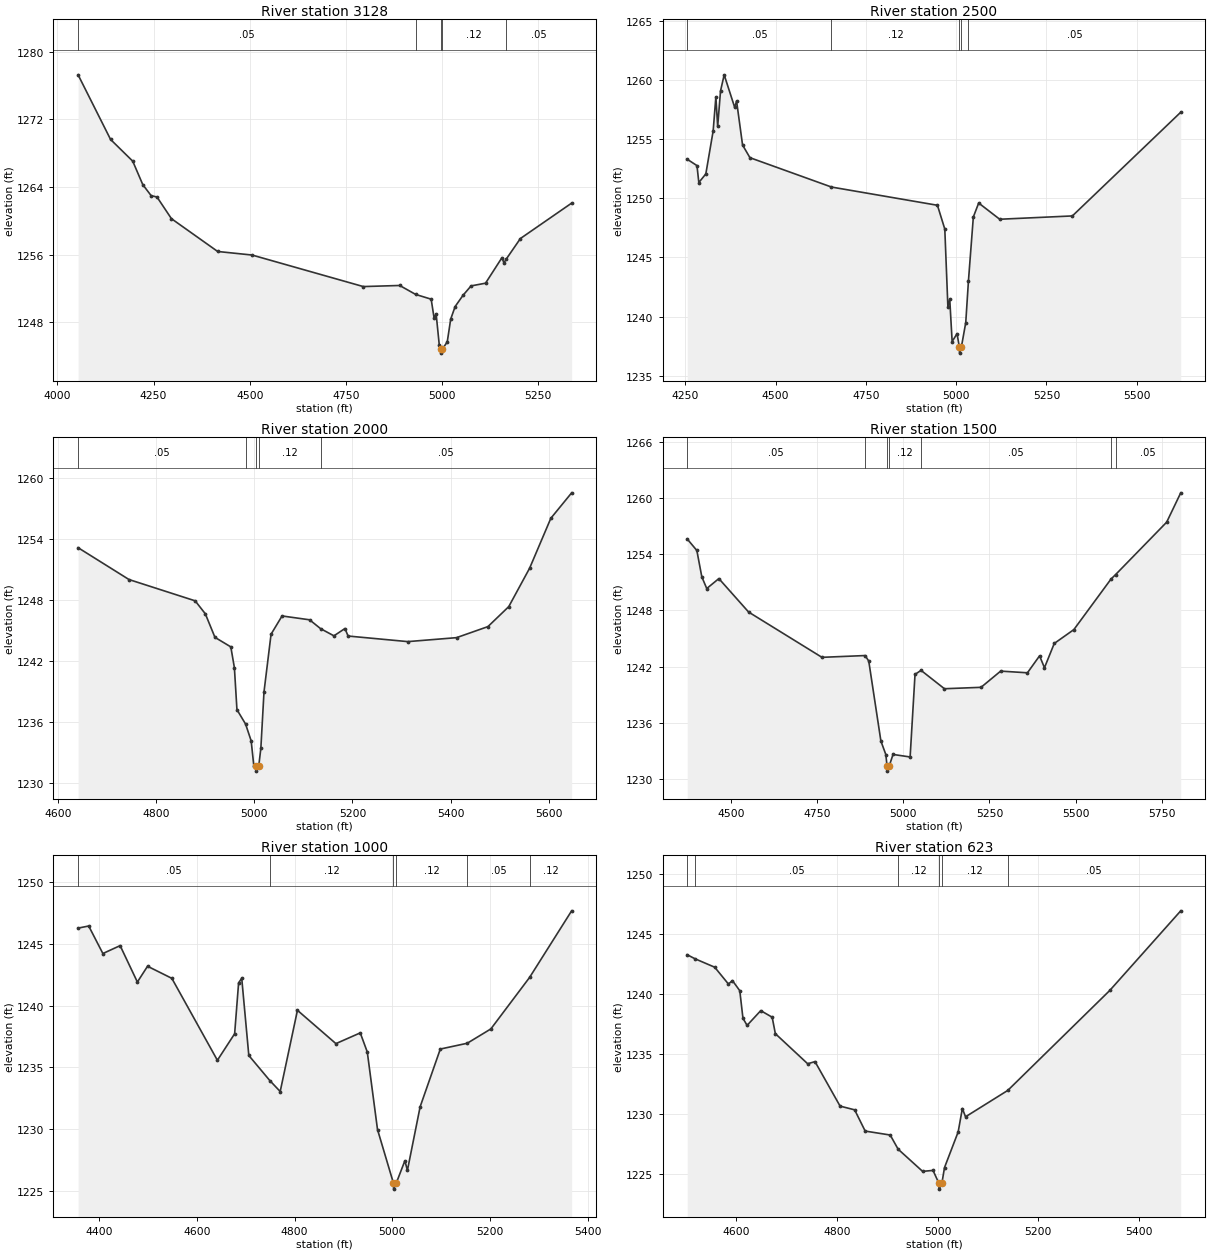
Type RM Length L Ch R = 1,3128,628,628,628
BEGIN DESCRIPTION:
SANFERNANDO006 6.0
END DESCRIPTION:
XS GIS Cut Line= 3
      2783005.67     10208003.11      2783902.75     10208304.00
      2784230.68     10208228.11
#Sta/Elev= 30
  4053.8 1277.28  4138.2 1269.64  4195.8 1267.07  4222.0 1264.29  4243.7 1262.99
  4258.9 1262.83  4296.4 1260.27  4416.6 1256.39  4505.9 1255.97  4795.1 1252.24
  4889.7 1252.37  4931.2 1251.31  4971.5 1250.75  4979.1 1248.52  4984.4 1249.01
  4992.5 1245.36  4996.9 1244.87  4997.2 1244.37  5000.9 1244.87  5013.3 1245.70
  5022.3 1248.40  5033.8 1249.88  5054.3 1251.21  5075.2 1252.32  5112.8 1252.64
  5155.5 1255.66  5160.6 1255.04  5166.3 1255.47  5203.4 1257.92  5336.6 1262.11
#Mann=5,-1,0
  4053.8    0.05       0  4931.2    0.12       0  4996.9    0.07       0
  5000.9    0.12       0  5166.3    0.05       0
Bank Sta=4996.9,5000.9
Exp/Cntr=0.3,0.1

Type RM Length L Ch R = 1,2500,500,500,500
BEGIN DESCRIPTION:
SANFERNANDO006 5.0
END DESCRIPTION:
XS GIS Cut Line= 3
      2783155.03     10208662.88      2783886.58     10208801.70
      2784397.53     10208447.35
#Sta/Elev= 30
  4255.4 1253.29  4282.5 1252.75  4287.6 1251.32  4307.0 1252.05  4327.3 1255.68
  4334.8 1258.56  4339.8 1256.06  4347.7 1259.06  4357.8 1260.42  4387.0 1257.66
  4392.1 1258.21  4408.7 1254.49  4429.1 1253.42  4654.9 1250.94  4948.2 1249.40
  4968.6 1247.39  4977.2 1240.78  4982.3 1241.46  4988.9 1237.89  5002.5 1238.55
  5009.0 1237.41  5009.4 1236.91  5014.4 1237.41  5026.6 1239.49  5034.1 1243.03
  5047.6 1248.41  5062.4 1249.59  5120.6 1248.22  5321.8 1248.50  5621.8 1257.26
#Mann=5,-1,0
  4255.4    0.05       0  4654.9    0.12       0  5009.0    0.07       0
  5014.4    0.12       0  5034.1    0.05       0
Bank Sta=5009,5014.4
Exp/Cntr=0.3,0.1

Type RM Length L Ch R = 1,2000,500,500,500
BEGIN DESCRIPTION:
SANFERNANDO006 4.0
END DESCRIPTION:
XS GIS Cut Line= 3
      2783805.73     10209303.10      2784151.69     10209207.96
      2784555.69     10208703.11
#Sta/Elev= 30
  4641.2 1253.16  4744.9 1250.02  4879.7 1247.92  4900.4 1246.64  4920.0 1244.32
  4952.3 1243.38  4959.6 1241.33  4964.8 1237.19  4982.4 1235.77  4993.8 1234.11
  4999.2 1231.63  5003.5 1231.63  5003.9 1231.13  5009.2 1231.63  5013.5 1233.38
  5019.9 1238.94  5034.3 1244.63  5056.7 1246.43  5112.8 1246.05  5135.1 1245.18
  5162.4 1244.47  5184.8 1245.19  5191.2 1244.45  5312.8 1243.90  5412.1 1244.29
  5476.1 1245.38  5518.5 1247.35  5561.0 1251.14  5604.2 1256.06  5646.6 1258.57
#Mann=5,-1,0
  4641.2    0.05       0  4982.4    0.12       0  5003.5    0.07       0
  5009.2    0.12       0  5135.1    0.05       0
Bank Sta=5003.5,5009.2
Exp/Cntr=0.3,0.1

Type RM Length L Ch R = 1,1500,500,500,500
BEGIN DESCRIPTION:
SANFERNANDO006 3.0
END DESCRIPTION:
XS GIS Cut Line= 3
      2784055.69     10209753.10      2784542.74     10209358.72
      2785144.51     10208824.03
#Sta/Elev= 30
  4373.3 1255.63  4401.3 1254.40  4415.7 1251.59  4430.0 1250.34  4465.2 1251.40
  4551.5 1247.83  4764.2 1243.00  4889.4 1243.19  4900.0 1242.60  4935.2 1234.07
  4949.6 1232.62  4953.1 1231.36  4953.6 1230.86  4958.9 1231.36  4970.4 1232.64
  5020.0 1232.37  5034.2 1241.18  5051.7 1241.61  5119.5 1239.65  5225.7 1239.80
  5282.6 1241.53  5360.3 1241.35  5395.5 1243.16  5409.7 1241.89  5438.1 1244.48
  5495.0 1245.96  5602.5 1251.34  5616.1 1251.83  5764.2 1257.42  5805.0 1260.55
#Mann=7,-1,0
  4373.3    0.05       0  4889.4    0.12       0  4953.1    0.07       0
  4958.9    0.12       0  5051.7    0.05       0  5602.5    0.12       0
  5616.1    0.05       0
Bank Sta=4953.1,4958.9
Exp/Cntr=0.3,0.1

Type RM Length L Ch R = 1,1000,377,377,377
BEGIN DESCRIPTION:
SANFERNANDO006 2.0
END DESCRIPTION:
XS GIS Cut Line= 3
      2784455.67     10209903.12      2784962.92     10209508.14
      2785055.67     10209153.15
#Sta/Elev= 30
  4357.1 1246.29  4378.8 1246.46  4407.8 1244.23  4443.1 1244.87  4478.4 1241.92
  4499.2 1243.20  4548.9 1242.22  4642.1 1235.58  4677.4 1237.73  4685.5 1241.85
  4691.9 1242.23  4706.4 1235.97  4749.3 1233.94  4770.6 1233.05  4805.9 1239.63
  4884.6 1236.93  4934.4 1237.80  4948.8 1236.25  4969.7 1229.97  5002.2 1225.64
  5002.7 1225.14  5008.2 1225.64  5025.7 1227.44  5030.9 1226.66  5056.9 1231.81
  5098.2 1236.49  5153.3 1236.96  5201.6 1238.12  5280.8 1242.29  5366.9 1247.69
#Mann=6,-1,0
  4357.1    0.05       0  4749.3    0.12       0  5002.2    0.07       0
  5008.2    0.12       0  5153.3    0.05       0  5280.8    0.12       0
Bank Sta=5002.2,5008.2
Exp/Cntr=0.3,0.1

Type RM Length L Ch R = 1,623,449,449,449
BEGIN DESCRIPTION:
Mapping XS 75596ee9
END DESCRIPTION:
XS GIS Cut Line= 3
      2784861.27     10210034.55      2785236.24     10209742.91
      2785541.25     10209340.85
#Sta/Elev= 30
  4503.0 1243.31  4518.7 1242.97  4557.6 1242.27  4584.8 1240.87  4592.9 1241.15
  4607.4 1240.31  4613.7 1238.01  4621.9 1237.42  4649.0 1238.65  4671.7 1238.10
  4678.0 1236.73  4742.2 1234.22  4756.7 1234.40  4806.5 1230.69  4835.4 1230.38
  4856.3 1228.61  4906.0 1228.28  4921.7 1227.10  4970.3 1225.25  4991.0 1225.33
  5002.5 1224.27  5003.0 1223.77  5008.6 1224.27  5013.8 1225.57  5040.9 1228.54
  5049.2 1230.49  5055.5 1229.80  5139.4 1232.00  5341.8 1240.33  5482.7 1246.97
#Mann=6,-1,0
  4503.0    0.12       0  4518.7    0.05       0  4921.7    0.12       0
  5002.5    0.07       0  5008.6    0.12       0  5139.4    0.05       0
Bank Sta=5002.5,5008.6
Exp/Cntr=0.3,0.1

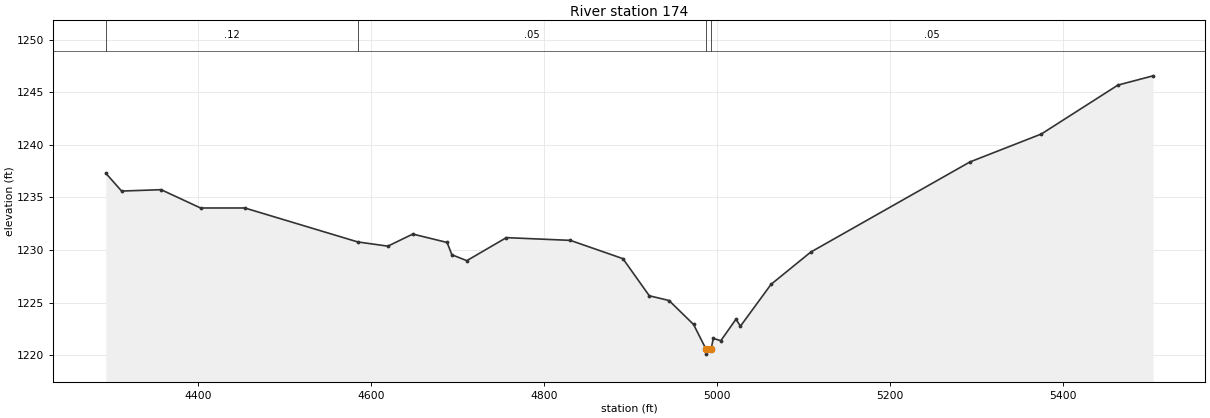
Type RM Length L Ch R = 1,174,0,0,0
BEGIN DESCRIPTION:
SANFERNANDO006 1.0
END DESCRIPTION:
XS GIS Cut Line= 3
      2785014.16     10210165.92      2785654.50     10209866.00
      2785780.67     10209378.15
#Sta/Elev= 30
  4292.9 1237.31  4311.2 1235.61  4356.9 1235.74  4402.5 1234.00  4453.7 1234.00
  4584.3 1230.77  4619.1 1230.37  4647.9 1231.52  4687.6 1230.72  4693.1 1229.55
  4710.4 1228.99  4756.1 1231.18  4830.1 1230.92  4890.9 1229.18  4921.4 1225.65
  4944.2 1225.20  4972.6 1222.92  4986.8 1220.60  4987.3 1220.10  4992.9 1220.60
  4995.4 1221.59  5004.1 1221.38  5021.6 1223.42  5026.8 1222.76  5062.2 1226.74
  5108.0 1229.80  5292.2 1238.38  5374.8 1241.04  5463.3 1245.69  5503.9 1246.57
#Mann=4,-1,0
  4292.9    0.12       0  4584.3    0.05       0  4986.8    0.03       0
  4992.9    0.05       0
Bank Sta=4986.8,4992.9
Exp/Cntr=0.3,0.1

Chan Stop Cuts=-1