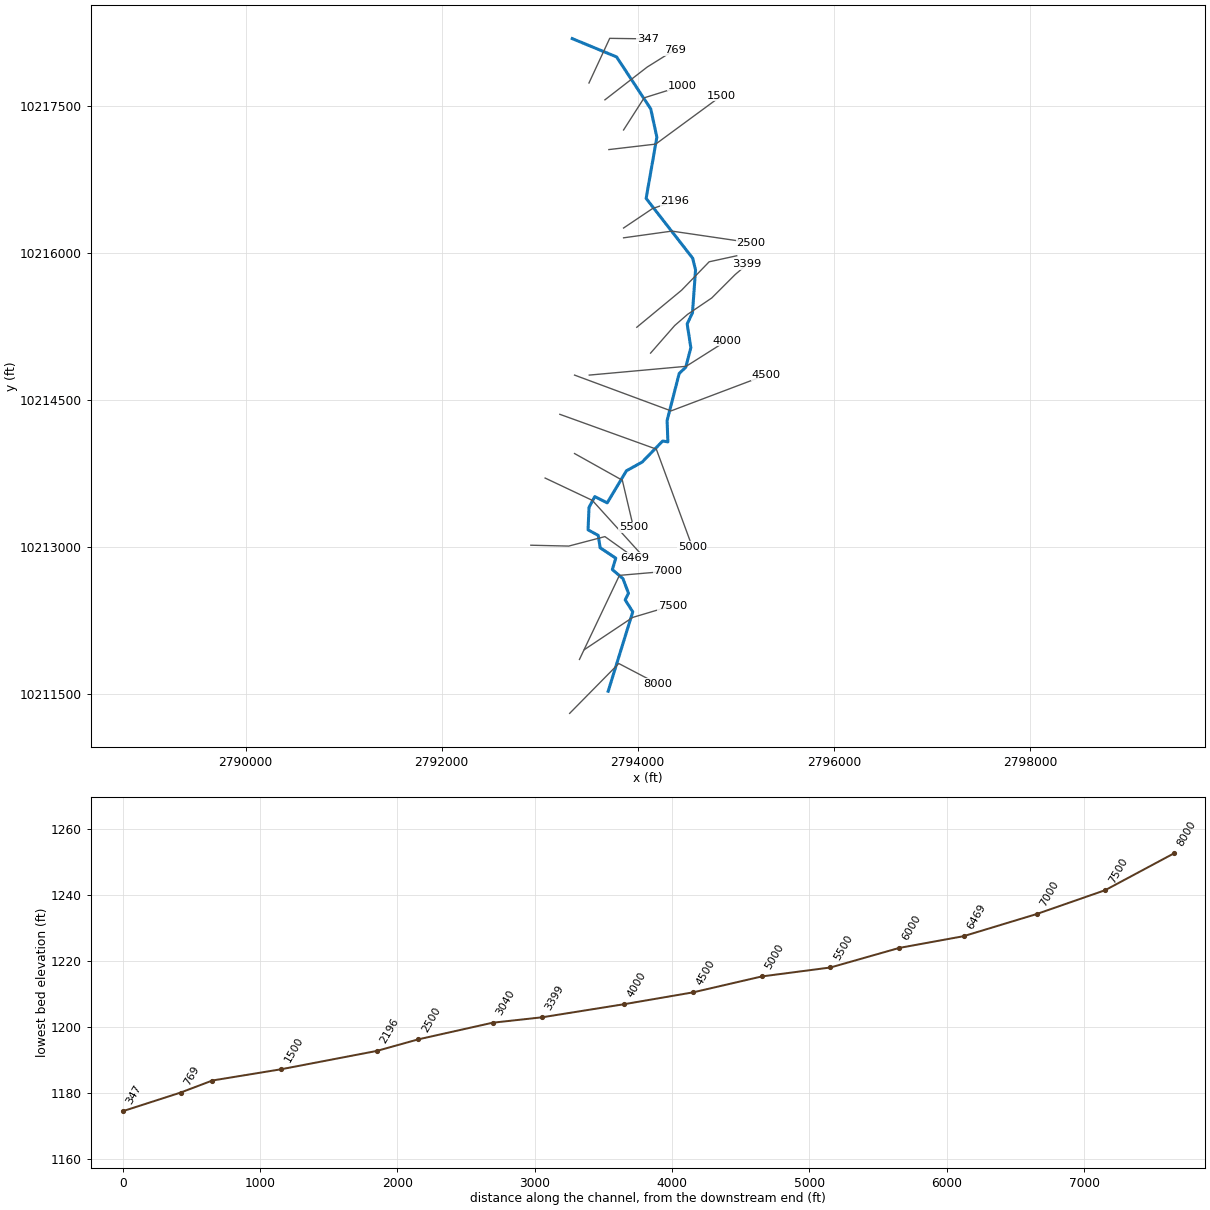
--- SANFERNANDO007.prj (project) ---

Proj Title=SANFERNANDO007 Base Level Engineering
Current Plan=p01
Default Exp/Contr=0.3,0.1
English Units
Geom File=g01
Flow File=f01
Plan File=p01
BEGIN DESCRIPTION:
SANFERNANDO007
END DESCRIPTION:

--- SANFERNANDO007.p01 (plan) ---

Plan Title=Multiple Run
Short Identifier=Multiple
Geom File=g01
Flow File=f01
Subcritical Flow
K Sum by GR= 0
Std Step Tol= 0.01
Critical Tol= 0.01
Num of Std Step Trials= 20
Max Error Tol= 0.3
Flow Tol Ratio= 0.001
Split Flow NTrial= 30
Split Flow Tol= 0.02
Split Flow Ratio= 0.02
Log Output Level= 0
Friction Slope Method= 1
Unsteady Friction Slope Method= 2
Unsteady Bridges Friction Slope Method= 1
Parabolic Critical Depth
Global Vel Dist=  1 , 1 , 1
Global Log Level= 0
CheckData=True
Encroach Param= -1, 0, 0, 0
BEGIN DESCRIPTION:
Multiple Run
END DESCRIPTION:

--- SANFERNANDO007.f01 (steady flow) ---

Flow Title=Multiple
Number of Profiles=7
Profile Names=10-year,25-year,50-year,1pct_min,100-year,1pct_plu,500-year
River Rch & RM= SANFERNANDO007,Reach-1,8000
     419     675    1418     969    1994    4103    2902
River Rch & RM= SANFERNANDO007,Reach-1,2500
     443     718    1481     907    2082    4778    3027
River Rch & RM= SANFERNANDO007,Reach-1,1500
     546     891    1995    1364    2835    5894    4112
Boundary for River Rch & Prof#=SANFERNANDO007,Reach-1,1
Up Type=0
Dn Type=3
Dn Slope=0.005
Boundary for River Rch & Prof#=SANFERNANDO007,Reach-1,2
Up Type=0
Dn Type=3
Dn Slope=0.005
Boundary for River Rch & Prof#=SANFERNANDO007,Reach-1,3
Up Type=0
Dn Type=3
Dn Slope=0.005
Boundary for River Rch & Prof#=SANFERNANDO007,Reach-1,4
Up Type=0
Dn Type=3
Dn Slope=0.005
Boundary for River Rch & Prof#=SANFERNANDO007,Reach-1,5
Up Type=0
Dn Type=3
Dn Slope=0.005
Boundary for River Rch & Prof#=SANFERNANDO007,Reach-1,6
Up Type=0
Dn Type=3
Dn Slope=0.005
Boundary for River Rch & Prof#=SANFERNANDO007,Reach-1,7
Up Type=0
Dn Type=3
Dn Slope=0.005

--- SANFERNANDO007.g01 (geometry) ---

Geom Title=Existing Conditions

River Reach=SANFERNANDO007,Reach-1
Reach XY= 30
      2793698.75     10211529.00      2793949.50     10212339.00
      2793872.25     10212460.00      2793905.75     10212529.00
      2793849.50     10212677.00      2793741.00     10212770.00
      2793776.25     10212886.00      2793616.75     10212992.00
      2793597.25     10213118.00      2793493.25     10213175.00
      2793503.50     10213404.00      2793562.00     10213514.00
      2793689.00     10213450.00      2793884.75     10213777.00
      2794045.25     10213866.00      2794254.75     10214081.00
      2794307.75     10214072.00      2794299.50     10214289.00
      2794423.00     10214770.00      2794489.75     10214833.00
      2794541.75     10215033.00      2794504.25     10215275.00
      2794558.50     10215389.00      2794589.75     10215825.00
      2794560.50     10215945.00      2794085.75     10216555.00
      2794195.25     10217180.00      2794132.75     10217468.00
      2793784.50     10217998.00      2793332.00     10218185.00

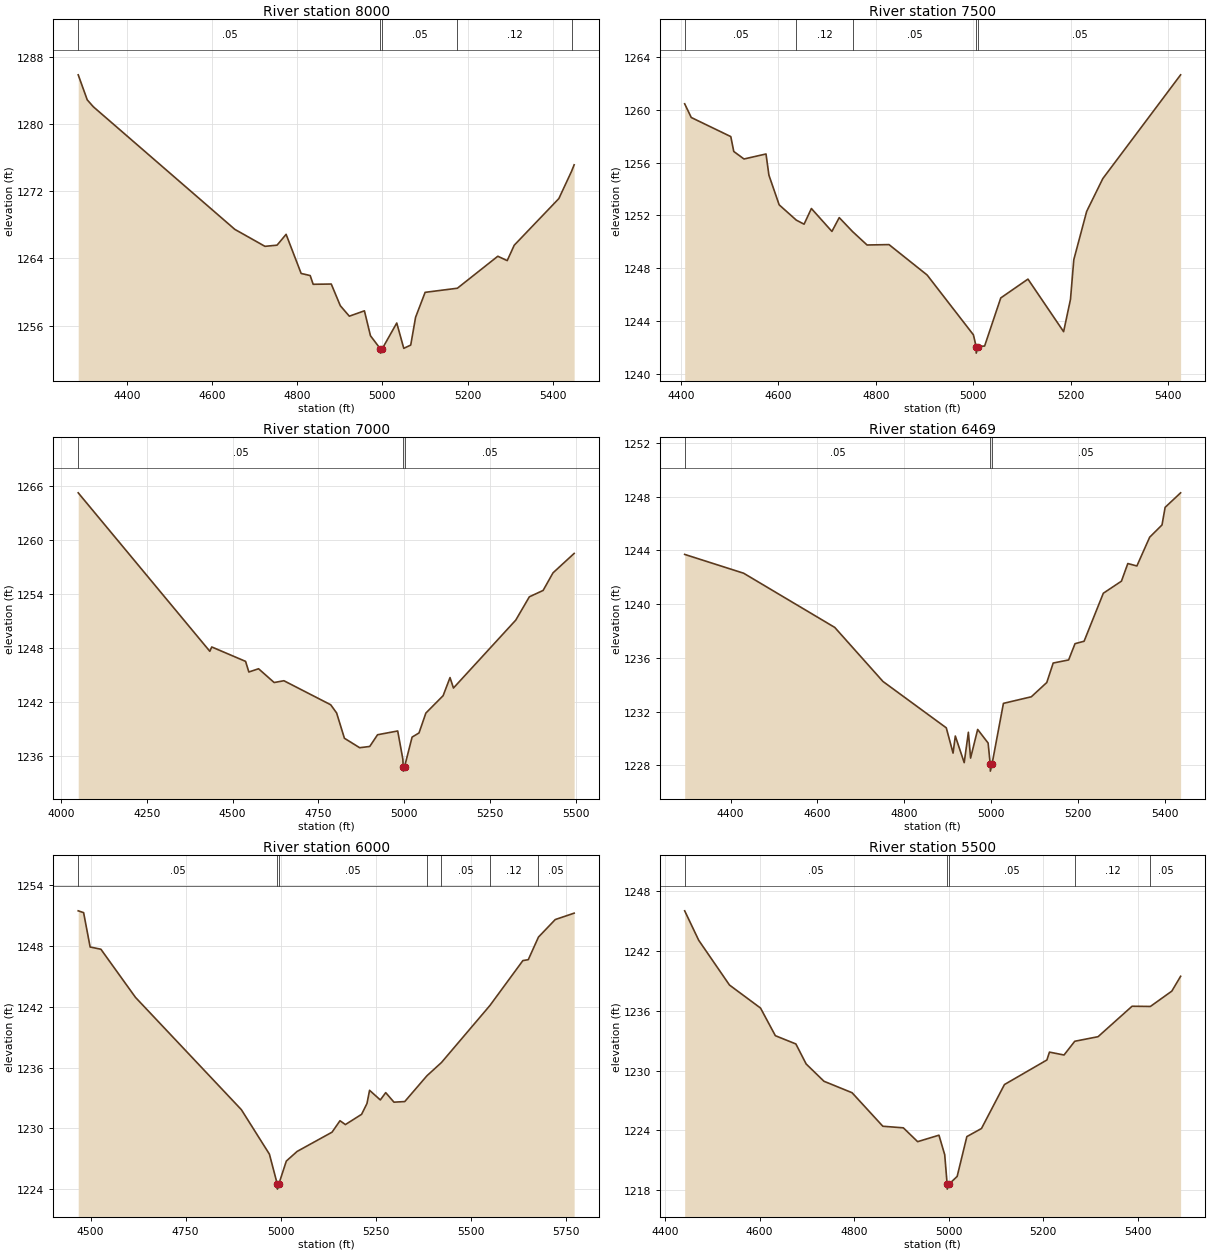
Type RM Length L Ch R = 1,8000,500,500,500
BEGIN DESCRIPTION:
SANFERNANDO007 16.0
END DESCRIPTION:
XS GIS Cut Line= 3
      2793305.68     10211303.10      2793806.68     10211811.68
      2794205.66     10211603.12
#Sta/Elev= 30
  4286.1 1285.86  4307.3 1282.88  4321.5 1282.06  4653.8 1267.45  4724.5 1265.43
  4752.8 1265.57  4774.1 1266.86  4809.4 1262.20  4830.6 1261.95  4837.6 1260.91
  4880.1 1260.94  4901.3 1258.36  4922.5 1257.11  4957.9 1257.75  4972.1 1254.78
  4995.5 1253.21  4995.7 1252.71  4999.5 1253.21  5033.8 1256.30  5050.3 1253.28
  5066.6 1253.67  5078.0 1256.98  5100.4 1259.95  5176.1 1260.44  5271.0 1264.25
  5293.1 1263.73  5309.5 1265.56  5414.3 1271.12  5444.2 1274.38  5450.2 1275.14
#Mann=5,-1,0
  4286.1    0.05       0  4995.5    0.05       0  4999.5    0.05       0
  5176.1    0.12       0  5444.2    0.05       0
Bank Sta=4995.5,4999.5
Exp/Cntr=0.3,0.1

Type RM Length L Ch R = 1,7500,500,500,500
BEGIN DESCRIPTION:
SANFERNANDO007 15.0
END DESCRIPTION:
XS GIS Cut Line= 3
      2793455.68     10211953.11      2793948.41     10212281.62
      2794355.68     10212403.11
#Sta/Elev= 30
  4407.8 1260.48  4421.3 1259.44  4502.4 1257.99  4508.5 1256.86  4529.5 1256.29
  4574.6 1256.67  4580.6 1255.06  4601.6 1252.81  4636.7 1251.65  4652.7 1251.34
  4667.7 1252.53  4709.8 1250.79  4724.8 1251.84  4752.1 1250.78  4781.9 1249.76
  4826.9 1249.79  4905.1 1247.48  5000.0 1242.94  5005.6 1242.05  5005.8 1241.55
  5009.6 1242.05  5023.0 1242.09  5056.1 1245.74  5111.9 1247.17  5185.0 1243.18
  5199.1 1245.63  5205.9 1248.64  5232.3 1252.31  5265.4 1254.80  5425.0 1262.68
#Mann=5,-1,0
  4407.8    0.05       0  4636.7    0.12       0  4752.1    0.05       0
  5005.6    0.03       0  5009.6    0.05       0
Bank Sta=5005.6,5009.6
Exp/Cntr=0.3,0.1

Type RM Length L Ch R = 1,7000,531,531,531
BEGIN DESCRIPTION:
SANFERNANDO007 14.0
END DESCRIPTION:
XS GIS Cut Line= 3
      2793405.69     10211853.13      2793813.27     10212710.60
      2794305.64     10212753.11
#Sta/Elev= 30
  4050.6 1265.20  4433.7 1247.60  4439.3 1248.08  4537.8 1246.48  4547.3 1245.30
  4575.6 1245.66  4621.0 1244.13  4649.3 1244.33  4785.6 1241.66  4802.8 1240.75
  4825.5 1237.94  4869.9 1236.89  4899.2 1237.03  4921.9 1238.33  4980.6 1238.75
  4995.6 1235.62  4996.6 1234.79  4996.9 1234.29  5000.6 1234.79  5022.5 1238.07
  5042.6 1238.53  5062.6 1240.74  5112.8 1242.67  5132.9 1244.68  5142.9 1243.52
  5324.2 1251.06  5363.8 1253.65  5403.9 1254.36  5432.6 1256.31  5494.2 1258.47
#Mann=3,-1,0
  4050.6    0.05       0  4996.6    0.05       0  5000.6    0.05       0
Bank Sta=4996.6,5000.6
Exp/Cntr=0.3,0.1

Type RM Length L Ch R = 1,6469,469,469,469
BEGIN DESCRIPTION:
Mapping XS 5c38f2a2
END DESCRIPTION:
XS GIS Cut Line= 4
      2792909.87     10213018.10      2793296.43     10213009.31
      2793665.43     10213105.95      2793970.57     10212888.00
#Sta/Elev= 30
  4294.0 1243.70  4429.9 1242.30  4639.9 1238.27  4751.0 1234.25  4897.0 1230.80
  4912.6 1228.92  4917.8 1230.19  4938.3 1228.21  4947.9 1230.47  4953.0 1228.55
  4969.3 1230.68  4993.4 1229.67  4998.3 1228.08  4998.6 1227.58  5002.3 1228.08
  5028.7 1232.62  5093.0 1233.11  5128.6 1234.17  5143.4 1235.62  5179.0 1235.85
  5193.7 1237.06  5214.6 1237.24  5258.9 1240.81  5300.7 1241.71  5315.4 1243.02
  5336.3 1242.84  5365.8 1244.98  5394.2 1245.89  5401.4 1247.20  5437.1 1248.28
#Mann=3,-1,0
  4294.0    0.05       0  4998.3    0.03       0  5002.3    0.05       0
Bank Sta=4998.3,5002.3
Exp/Cntr=0.3,0.1

Type RM Length L Ch R = 1,6000,500,500,500
BEGIN DESCRIPTION:
SANFERNANDO007 12.0
END DESCRIPTION:
XS GIS Cut Line= 3
      2793055.67     10213703.12      2793537.12     10213475.38
      2794055.70     10212903.09
#Sta/Elev= 30
  4467.4 1251.47  4481.6 1251.29  4498.8 1247.90  4527.1 1247.68  4618.1 1242.93
  4896.7 1231.85  4970.5 1227.46  4991.2 1224.51  4991.5 1224.01  4995.2 1224.51
  5015.0 1226.78  5043.4 1227.73  5135.3 1229.63  5156.2 1230.76  5170.4 1230.38
  5213.0 1231.39  5227.2 1232.46  5234.0 1233.76  5262.3 1232.81  5276.5 1233.53
  5298.2 1232.59  5326.6 1232.65  5384.8 1235.19  5423.1 1236.50  5550.7 1242.13
  5637.4 1246.56  5651.6 1246.65  5678.4 1248.88  5722.6 1250.61  5772.3 1251.24
#Mann=7,-1,0
  4467.4    0.05       0  4991.2    0.05       0  4995.2    0.05       0
  5384.8    0.12       0  5423.1    0.05       0  5550.7    0.12       0
  5678.4    0.05       0
Bank Sta=4991.2,4995.2
Exp/Cntr=0.3,0.1

Type RM Length L Ch R = 1,5500,500,500,500
BEGIN DESCRIPTION:
SANFERNANDO007 11.0
END DESCRIPTION:
XS GIS Cut Line= 3
      2793355.69     10213953.11      2793843.04     10213680.52
      2793955.68     10213203.13
#Sta/Elev= 30
  4441.6 1246.05  4471.3 1243.09  4536.4 1238.59  4602.0 1236.28  4633.4 1233.50
  4676.8 1232.67  4698.5 1230.66  4736.2 1228.92  4795.6 1227.77  4860.7 1224.40
  4904.1 1224.24  4934.3 1222.85  4979.4 1223.50  4991.6 1221.53  4996.7 1218.58
  4996.9 1218.08  5000.7 1218.58  5017.9 1219.36  5038.4 1223.36  5069.3 1224.17
  5117.9 1228.59  5207.7 1231.06  5213.1 1231.85  5243.9 1231.56  5266.6 1232.94
  5315.9 1233.40  5387.8 1236.46  5426.6 1236.44  5471.9 1237.98  5490.5 1239.47
#Mann=5,-1,0
  4441.6    0.05       0  4996.7    0.03       0  5000.7    0.05       0
  5266.6    0.12       0  5426.6    0.05       0
Bank Sta=4996.7,5000.7
Exp/Cntr=0.3,0.1

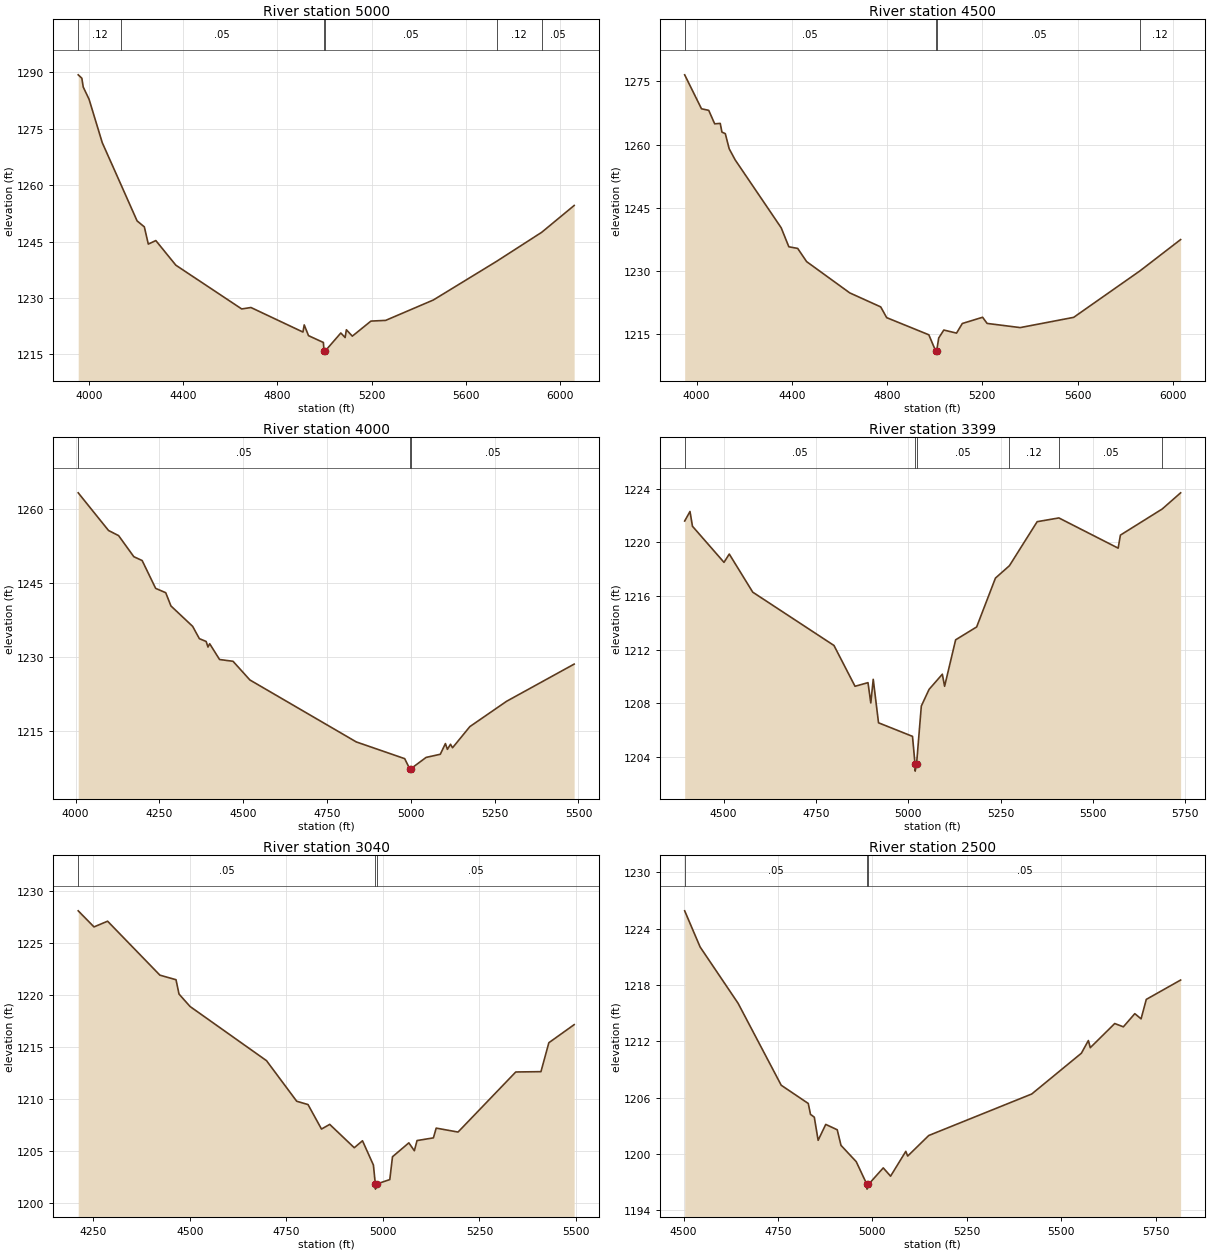
Type RM Length L Ch R = 1,5000,500,500,500
BEGIN DESCRIPTION:
SANFERNANDO007 10.0
END DESCRIPTION:
XS GIS Cut Line= 3
      2793205.67     10214353.12      2794189.65     10213998.01
      2794555.69     10213003.11
#Sta/Elev= 30
  3953.9 1289.31  3969.3 1288.41  3975.2 1286.07  3999.9 1282.83  4056.0 1271.29
  4133.7 1260.38  4204.0 1250.49  4234.7 1248.91  4251.6 1244.33  4283.5 1245.27
  4368.5 1238.73  4648.2 1227.10  4687.5 1227.48  4908.4 1220.96  4913.7 1222.86
  4932.0 1220.00  4995.1 1218.19  4997.9 1215.86  4998.1 1215.36  5001.9 1215.86
  5069.2 1220.71  5087.5 1219.50  5092.8 1221.57  5118.0 1219.87  5197.0 1223.87
  5259.6 1224.06  5462.2 1229.48  5731.3 1239.77  5922.6 1247.48  6060.1 1254.59
#Mann=6,-1,0
  3953.9    0.12       0  4133.7    0.05       0  4997.9    0.05       0
  5001.9    0.05       0  5731.3    0.12       0  5922.6    0.05       0
Bank Sta=4997.9,5001.9
Exp/Cntr=0.3,0.1

Type RM Length L Ch R = 1,4500,500,500,500
BEGIN DESCRIPTION:
SANFERNANDO007 9.0
END DESCRIPTION:
XS GIS Cut Line= 3
      2793355.70     10214753.11      2794339.98     10214388.06
      2795305.68     10214753.11
#Sta/Elev= 30
  3950.2 1276.58  4020.8 1268.52  4051.2 1268.15  4076.2 1264.95  4099.5 1265.05
  4106.6 1262.99  4120.8 1262.62  4137.0 1259.04  4162.0 1256.41  4355.5 1240.27
  4387.5 1235.77  4424.7 1235.38  4462.1 1232.25  4643.5 1224.82  4773.3 1221.50
  4798.3 1218.95  4975.3 1214.88  5004.1 1211.03  5004.3 1210.53  5008.1 1211.03
  5016.8 1214.13  5038.2 1216.01  5091.6 1215.28  5115.8 1217.56  5201.0 1219.04
  5219.9 1217.58  5358.9 1216.59  5583.4 1219.02  5862.2 1230.07  6032.4 1237.48
#Mann=4,-1,0
  3950.2    0.05       0  5004.1    0.05       0  5008.1    0.05       0
  5862.2    0.12       0
Bank Sta=5004.1,5008.1
Exp/Cntr=0.3,0.1

Type RM Length L Ch R = 1,4000,601,601,601
BEGIN DESCRIPTION:
SANFERNANDO007 8.0
END DESCRIPTION:
XS GIS Cut Line= 3
      2793505.67     10214753.11      2794493.92     10214842.68
      2794905.68     10215103.11
#Sta/Elev= 30
  4007.7 1263.20  4098.1 1255.59  4128.2 1254.55  4173.6 1250.29  4198.5 1249.51
  4238.7 1243.89  4268.8 1243.01  4284.3 1240.34  4349.1 1236.21  4369.2 1233.72
  4389.3 1233.16  4394.9 1232.03  4399.9 1232.70  4429.4 1229.51  4469.6 1229.15
  4519.8 1225.38  4837.3 1212.85  4981.7 1209.47  4996.4 1207.45  4996.6 1206.95
  5000.4 1207.45  5045.5 1209.72  5087.9 1210.36  5103.2 1212.52  5109.1 1211.35
  5118.4 1212.38  5124.4 1211.67  5176.1 1215.95  5285.5 1221.06  5487.2 1228.58
#Mann=3,-1,0
  4007.7    0.05       0  4996.4    0.03       0  5000.4    0.05       0
Bank Sta=4996.4,5000.4
Exp/Cntr=0.3,0.1

Type RM Length L Ch R = 1,3399,359,359,359
BEGIN DESCRIPTION:
Mapping XS 81682e08
END DESCRIPTION:
XS GIS Cut Line= 6
      2794131.09     10214977.35      2794377.09     10215258.49
      2794508.87     10215372.71      2794754.88     10215539.64
      2794992.10     10215776.85      2795115.07     10215882.26
#Sta/Elev= 30
  4394.7 1221.58  4409.1 1222.29  4415.8 1221.19  4501.2 1218.50  4515.4 1219.12
  4579.0 1216.28  4798.9 1212.31  4855.9 1209.27  4891.0 1209.54  4898.6 1208.03
  4905.2 1209.79  4919.5 1206.55  5011.5 1205.54  5018.4 1203.45  5018.7 1202.95
  5022.4 1203.45  5035.4 1207.80  5056.4 1209.04  5092.3 1210.17  5098.4 1209.27
  5128.3 1212.73  5185.2 1213.69  5236.1 1217.33  5273.9 1218.25  5349.0 1221.53
  5407.8 1221.81  5568.3 1219.56  5574.4 1220.53  5687.8 1222.48  5737.4 1223.68
#Mann=6,-1,0
  4394.7    0.05       0  5018.4    0.03       0  5022.4    0.05       0
  5273.9    0.12       0  5407.8    0.05       0  5687.8    0.12       0
Bank Sta=5018.4,5022.4
Exp/Cntr=0.3,0.1

Type RM Length L Ch R = 1,3040,540,540,540
BEGIN DESCRIPTION:
Mapping XS 0bbb8489
END DESCRIPTION:
XS GIS Cut Line= 4
      2793990.49     10215240.90      2794447.37     10215618.71
      2794728.52     10215908.64      2795009.66     10215970.14
#Sta/Elev= 30
  4210.9 1228.13  4251.8 1226.58  4287.0 1227.13  4422.5 1221.93  4464.2 1221.49
  4472.0 1220.11  4500.6 1218.91  4698.6 1213.69  4776.8 1209.78  4806.1 1209.46
  4841.0 1207.10  4862.3 1207.55  4925.9 1205.30  4947.2 1205.97  4975.5 1203.63
  4980.4 1201.81  4980.7 1201.31  4984.4 1201.81  5017.9 1202.23  5024.9 1204.43
  5067.3 1205.77  5081.5 1205.01  5088.5 1205.99  5130.9 1206.25  5138.1 1207.19
  5194.7 1206.81  5344.2 1212.60  5409.4 1212.63  5429.9 1215.42  5495.4 1217.16
#Mann=3,-1,0
  4210.9    0.05       0  4980.4    0.05       0  4984.4    0.05       0
Bank Sta=4980.4,4984.4
Exp/Cntr=0.3,0.1

Type RM Length L Ch R = 1,2500,304,304,304
BEGIN DESCRIPTION:
SANFERNANDO007 5.0
END DESCRIPTION:
XS GIS Cut Line= 3
      2793855.66     10216153.11      2794348.11     10216221.65
      2795155.66     10216103.12
#Sta/Elev= 30
  4502.8 1225.90  4543.7 1222.05  4644.2 1216.06  4758.5 1207.33  4830.1 1205.39
  4836.0 1204.23  4846.1 1203.93  4856.2 1201.47  4876.4 1203.16  4906.8 1202.59
  4916.8 1200.93  4957.2 1199.19  4985.4 1196.77  4985.7 1196.27  4989.5 1196.77
  5028.7 1198.53  5048.1 1197.65  5088.4 1200.29  5093.4 1199.79  5149.2 1201.98
  5422.0 1206.40  5553.4 1210.74  5571.9 1212.09  5577.0 1211.33  5641.7 1213.90
  5664.6 1213.55  5694.9 1214.95  5711.5 1214.40  5725.3 1216.47  5816.2 1218.53
#Mann=3,-1,0
  4502.8    0.05       0  4985.4    0.05       0  4989.5    0.05       0
Bank Sta=4985.4,4989.5
Exp/Cntr=0.3,0.1

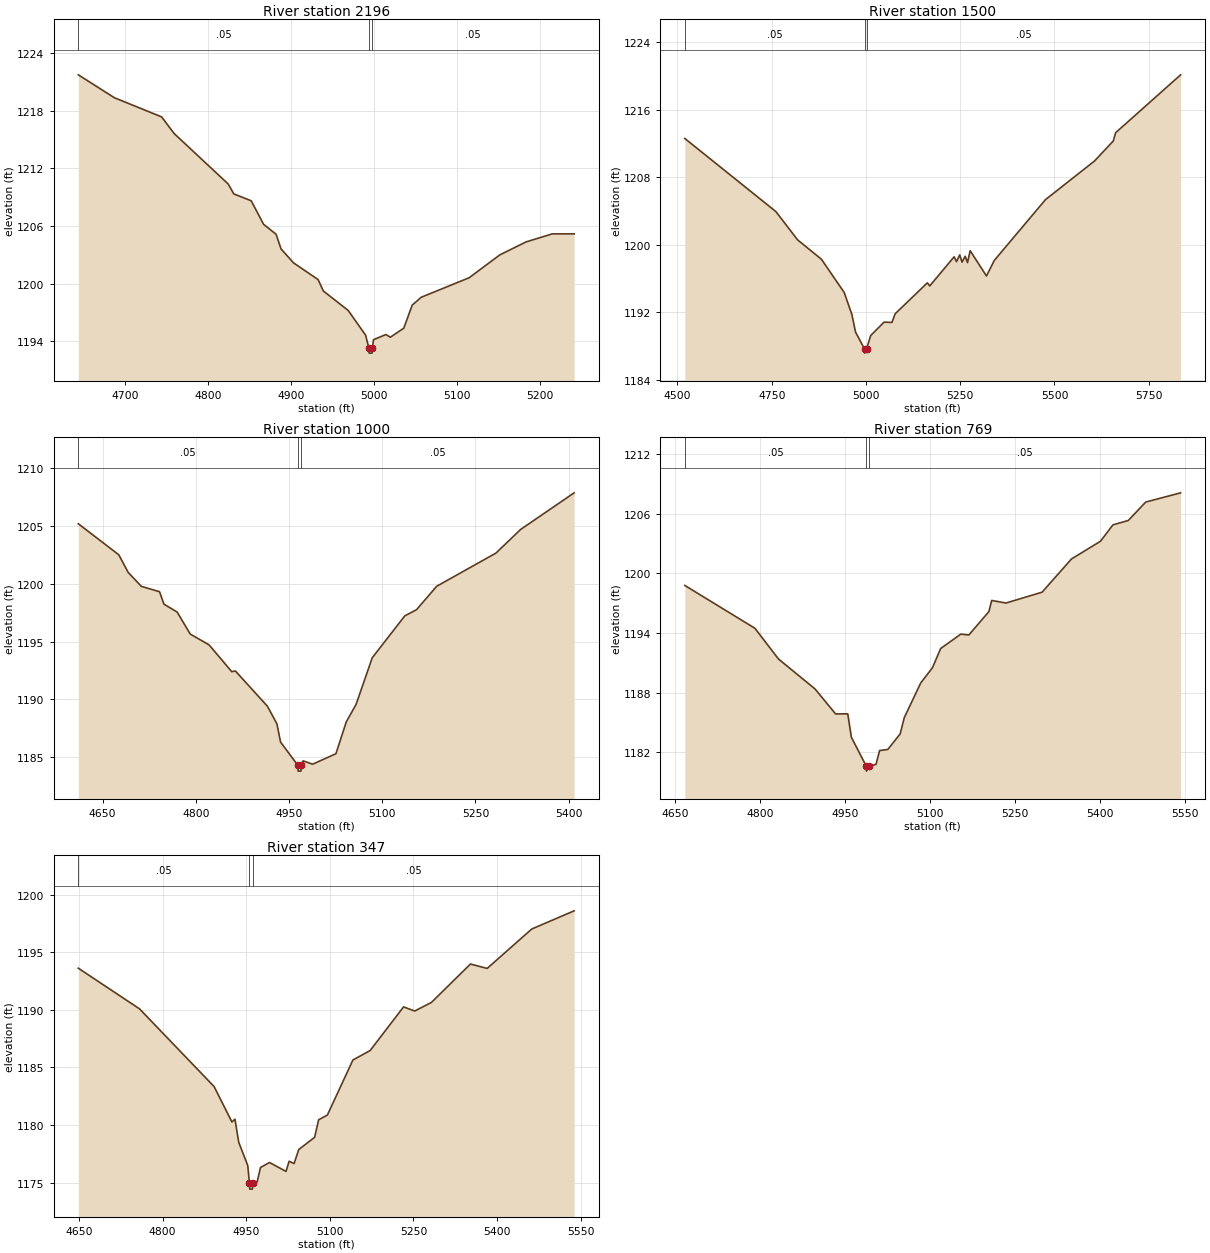
Type RM Length L Ch R = 1,2196,696,696,696
BEGIN DESCRIPTION:
SANFERNANDO007 4.0
END DESCRIPTION:
XS GIS Cut Line= 3
      2793855.65     10216253.09      2794151.50     10216452.00
      2794380.69     10216528.11
#Sta/Elev= 30
  4643.5 1221.77  4687.0 1219.38  4744.0 1217.38  4759.0 1215.65  4824.3 1210.38
  4831.0 1209.35  4852.0 1208.63  4867.0 1206.17  4882.0 1205.14  4888.0 1203.61
  4903.0 1202.16  4932.7 1200.41  4939.0 1199.22  4968.9 1197.20  4990.0 1194.61
  4994.0 1193.24  4994.2 1192.74  4997.8 1192.74  4998.1 1193.24  4999.5 1194.14
  5014.5 1194.68  5019.8 1194.40  5036.0 1195.34  5046.2 1197.75  5057.1 1198.57
  5114.8 1200.60  5151.9 1202.99  5183.5 1204.34  5215.1 1205.18  5241.5 1205.18
#Mann=3,-1,0
  4643.5    0.05       0  4994.0    0.03       0  4998.1    0.05       0
Bank Sta=4994,4998.1
Exp/Cntr=0.3,0.1

Type RM Length L Ch R = 1,1500,500,500,500
BEGIN DESCRIPTION:
SANFERNANDO007 3.0
END DESCRIPTION:
XS GIS Cut Line= 3
      2793705.71     10217053.11      2794183.05     10217108.95
      2794855.65     10217603.08
#Sta/Elev= 30
  4519.4 1212.58  4761.0 1203.93  4818.5 1200.59  4881.8 1198.29  4942.2 1194.36
  4962.4 1191.78  4972.4 1189.66  4996.1 1187.68  4996.6 1187.18  5001.5 1187.68
  5012.5 1189.26  5048.0 1190.85  5068.8 1190.81  5077.3 1191.83  5162.9 1195.50
  5169.1 1195.13  5233.9 1198.58  5240.1 1198.00  5248.6 1198.80  5254.8 1197.95
  5263.2 1198.64  5269.4 1197.89  5276.3 1199.30  5319.6 1196.31  5340.4 1198.15
  5476.3 1205.35  5605.9 1209.90  5656.0 1212.28  5662.2 1213.26  5834.6 1220.11
#Mann=3,-1,0
  4519.4    0.05       0  4996.1    0.05       0  5001.5    0.05       0
Bank Sta=4996.1,5001.5
Exp/Cntr=0.3,0.1

Type RM Length L Ch R = 1,1000,231,231,231
BEGIN DESCRIPTION:
SANFERNANDO007 2.0
END DESCRIPTION:
XS GIS Cut Line= 3
      2793855.66     10217253.08      2794065.56     10217580.71
      2794455.71     10217703.12
#Sta/Elev= 30
  4610.9 1205.21  4676.0 1202.52  4691.2 1200.99  4712.4 1199.78  4741.6 1199.32
  4748.7 1198.24  4769.9 1197.56  4791.0 1195.65  4821.4 1194.71  4857.8 1192.39
  4863.7 1192.45  4915.3 1189.39  4930.5 1187.87  4936.4 1186.29  4964.2 1184.27
  4964.6 1183.77  4969.2 1183.77  4969.6 1184.27  4972.8 1184.66  4988.0 1184.37
  5025.5 1185.28  5042.1 1188.03  5057.9 1189.55  5084.0 1193.60  5136.4 1197.23
  5155.2 1197.76  5187.6 1199.79  5283.1 1202.67  5322.6 1204.71  5408.9 1207.89
#Mann=3,-1,0
  4610.9    0.05       0  4964.2    0.05       0  4969.6    0.05       0
Bank Sta=4964.2,4969.6
Exp/Cntr=0.3,0.1

Type RM Length L Ch R = 1,769,422,422,422
BEGIN DESCRIPTION:
Mapping XS 7d3dc394
END DESCRIPTION:
XS GIS Cut Line= 3
      2793665.45     10217560.40      2794095.94     10217894.25
      2794375.63     10218069.05
#Sta/Elev= 30
  4667.1 1198.78  4790.8 1194.47  4832.4 1191.38  4896.7 1188.38  4933.1 1185.86
  4954.6 1185.87  4960.9 1183.52  4987.2 1180.61  4987.6 1180.11  4992.6 1180.61
  5004.4 1180.79  5010.7 1182.18  5025.2 1182.29  5047.0 1183.85  5054.2 1185.48
  5083.2 1188.97  5104.0 1190.51  5118.5 1192.44  5153.8 1193.88  5168.2 1193.80
  5203.5 1196.15  5208.5 1197.27  5233.6 1197.01  5297.3 1198.10  5349.2 1201.44
  5400.3 1203.22  5422.3 1204.87  5449.4 1205.31  5480.1 1207.16  5541.7 1208.09
#Mann=3,-1,0
  4667.1    0.05       0  4987.2    0.05       0  4992.6    0.05       0
Bank Sta=4987.2,4992.6
Exp/Cntr=0.3,0.1

Type RM Length L Ch R = 1,347,0,0,0
BEGIN DESCRIPTION:
SANFERNANDO007 1.0
END DESCRIPTION:
XS GIS Cut Line= 3
      2793502.76     10217732.07      2793714.40     10218187.61
      2794101.76     10218182.07
#Sta/Elev= 30
  4648.8 1193.62  4758.6 1190.09  4892.5 1183.34  4924.4 1180.27  4929.9 1180.51
  4936.6 1178.51  4952.8 1176.49  4955.9 1174.94  4956.4 1174.44  4961.0 1174.44
  4961.4 1174.94  4969.7 1175.07  4975.7 1176.32  4991.8 1176.75  5021.5 1175.98
  5027.0 1176.86  5035.9 1176.66  5044.4 1177.88  5072.8 1178.94  5080.0 1180.46
  5095.7 1180.87  5141.5 1185.65  5172.4 1186.47  5232.4 1190.26  5252.4 1189.90
  5282.4 1190.65  5352.4 1193.98  5382.4 1193.60  5462.4 1197.02  5538.5 1198.60
#Mann=3,-1,0
  4648.8    0.05       0  4955.9    0.03       0  4961.4    0.05       0
Bank Sta=4955.9,4961.4
Exp/Cntr=0.3,0.1

Chan Stop Cuts=-1