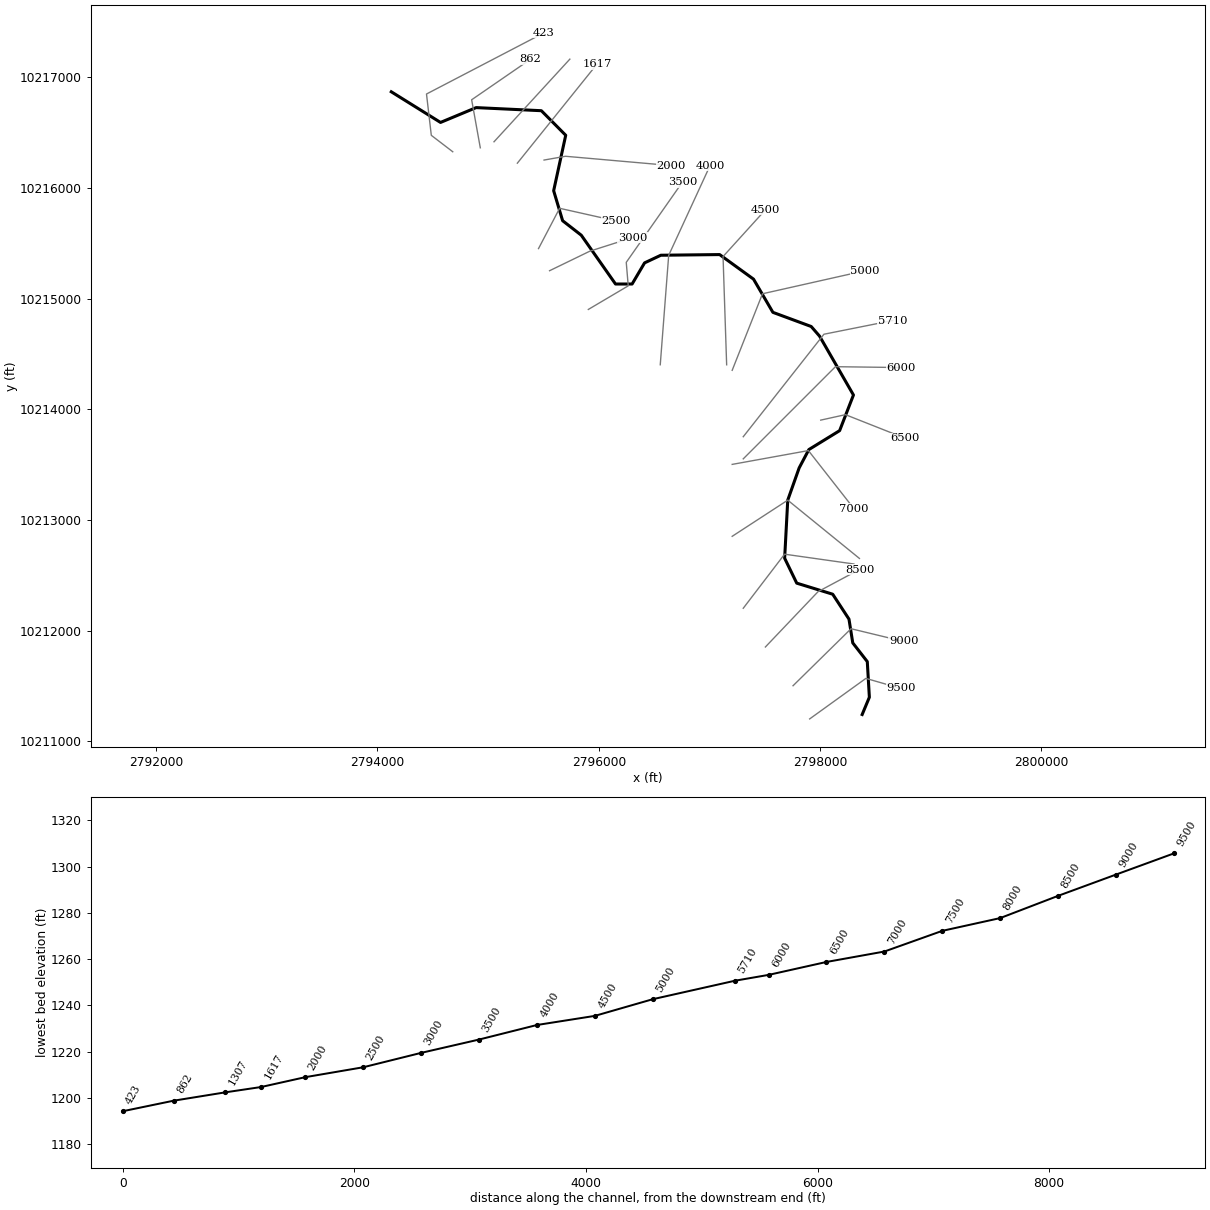
--- SANFERNANDO008.prj (project) ---

Proj Title=SANFERNANDO008 Base Level Engineering
Current Plan=p01
Default Exp/Contr=0.3,0.1
English Units
Geom File=g01
Flow File=f01
Plan File=p01
BEGIN DESCRIPTION:
SANFERNANDO008
END DESCRIPTION:

--- SANFERNANDO008.p01 (plan) ---

Plan Title=Multiple Run
Short Identifier=Multiple
Geom File=g01
Flow File=f01
Subcritical Flow
K Sum by GR= 0
Std Step Tol= 0.01
Critical Tol= 0.01
Num of Std Step Trials= 20
Max Error Tol= 0.3
Flow Tol Ratio= 0.001
Split Flow NTrial= 30
Split Flow Tol= 0.02
Split Flow Ratio= 0.02
Log Output Level= 0
Friction Slope Method= 1
Unsteady Friction Slope Method= 2
Unsteady Bridges Friction Slope Method= 1
Parabolic Critical Depth
Global Vel Dist=  1 , 1 , 1
Global Log Level= 0
CheckData=True
Encroach Param= -1, 0, 0, 0
BEGIN DESCRIPTION:
Multiple Run
END DESCRIPTION:

--- SANFERNANDO008.f01 (steady flow) ---

Flow Title=Multiple
Number of Profiles=7
Profile Names=10-year,25-year,50-year,1pct_min,100-year,1pct_plu,500-year
River Rch & RM= SANFERNANDO008,Reach-1,9500
     368     594     929     575    1265    2786    1804
Boundary for River Rch & Prof#=SANFERNANDO008,Reach-1,1
Up Type=0
Dn Type=3
Dn Slope=0.005
Boundary for River Rch & Prof#=SANFERNANDO008,Reach-1,2
Up Type=0
Dn Type=3
Dn Slope=0.005
Boundary for River Rch & Prof#=SANFERNANDO008,Reach-1,3
Up Type=0
Dn Type=3
Dn Slope=0.005
Boundary for River Rch & Prof#=SANFERNANDO008,Reach-1,4
Up Type=0
Dn Type=3
Dn Slope=0.005
Boundary for River Rch & Prof#=SANFERNANDO008,Reach-1,5
Up Type=0
Dn Type=3
Dn Slope=0.005
Boundary for River Rch & Prof#=SANFERNANDO008,Reach-1,6
Up Type=0
Dn Type=3
Dn Slope=0.005
Boundary for River Rch & Prof#=SANFERNANDO008,Reach-1,7
Up Type=0
Dn Type=3
Dn Slope=0.005

--- SANFERNANDO008.g01 (geometry) ---

Geom Title=Existing Conditions

River Reach=SANFERNANDO008,Reach-1
Reach XY= 30
      2798380.25     10211243.00      2798445.25     10211399.00
      2798426.50     10211721.00      2798295.25     10211890.00
      2798261.00     10212105.00      2798114.00     10212330.00
      2797789.00     10212430.00      2797679.75     10212655.00
      2797707.75     10213180.00      2797810.75     10213471.00
      2797898.50     10213637.00      2798176.50     10213808.00
      2798301.50     10214130.00      2797995.25     10214662.00
      2797919.75     10214749.00      2797573.50     10214877.00
      2797398.50     10215177.00      2797092.25     10215399.00
      2796561.00     10215393.00      2796414.00     10215324.00
      2796301.50     10215133.00      2796151.50     10215133.00
      2795842.00     10215574.00      2795673.50     10215705.00
      2795592.50     10215976.00      2795701.50     10216477.00
      2795481.50     10216699.00      2794892.00     10216727.00
      2794570.25     10216593.00      2794125.25     10216870.00

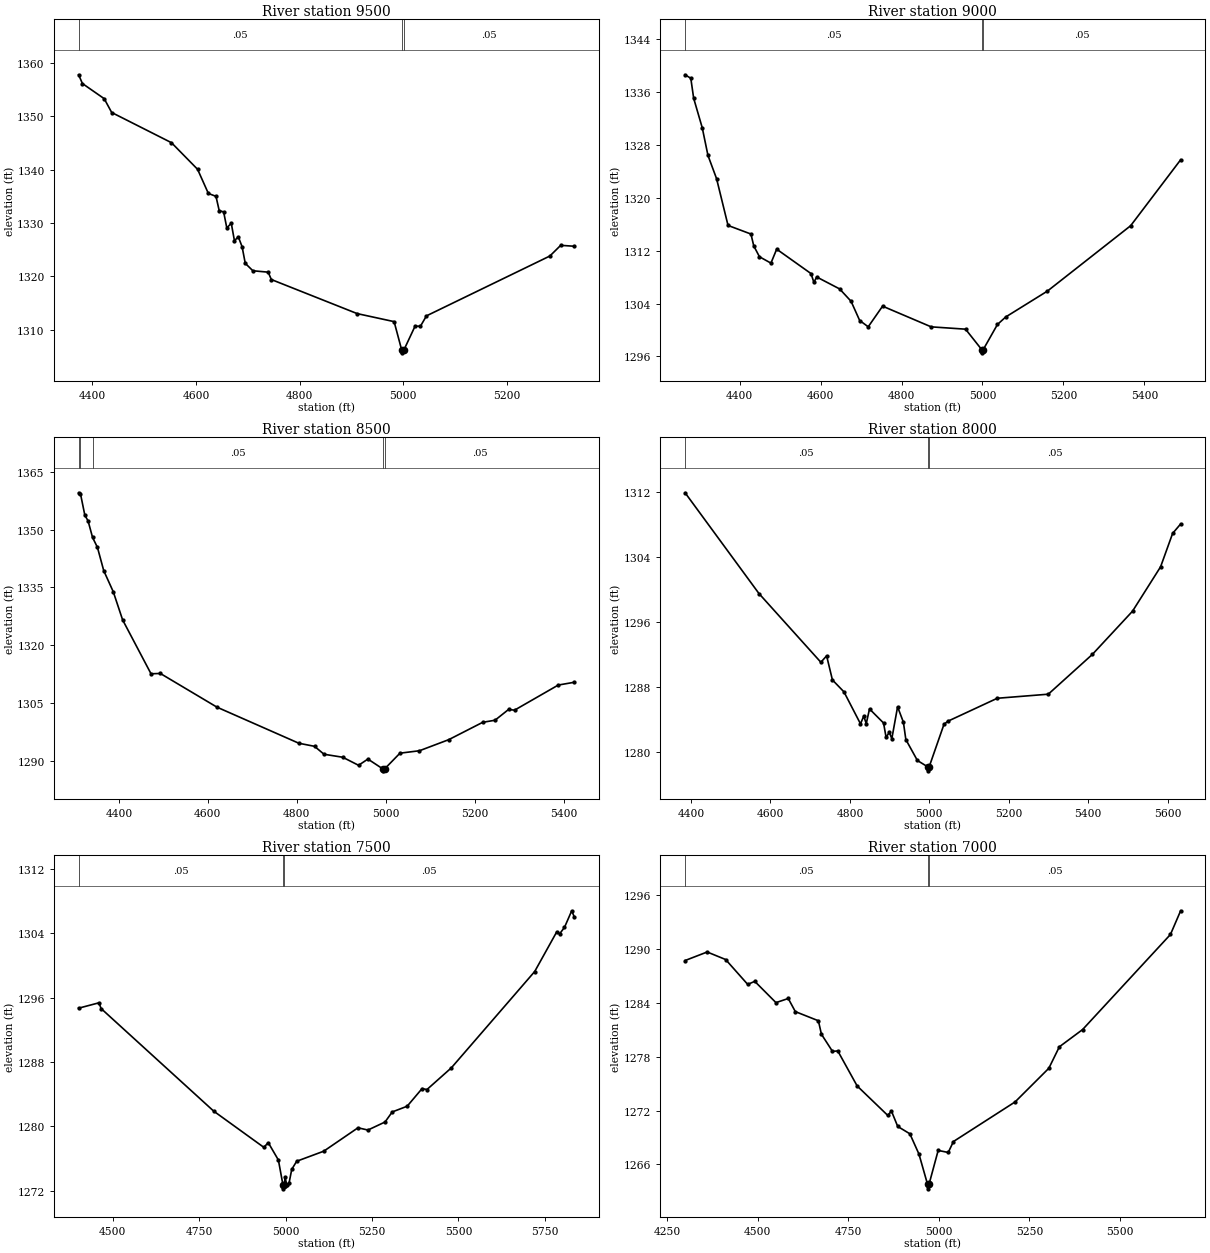
Type RM Length L Ch R = 1,9500,500,500,500
BEGIN DESCRIPTION:
SANFERNANDO008 19.0
END DESCRIPTION:
XS GIS Cut Line= 3
      2797905.70     10211203.12      2798414.00     10211569.37
      2798730.71     10211478.10
#Sta/Elev= 30
  4373.5 1357.74  4380.8 1356.10  4422.8 1353.27  4437.3 1350.68  4552.6 1345.03
  4603.0 1340.05  4623.8 1335.53  4638.5 1334.99  4644.7 1332.32  4653.3 1332.07
  4659.4 1329.07  4668.0 1329.96  4674.1 1326.69  4681.6 1327.41  4688.9 1325.56
  4695.0 1322.45  4709.7 1321.06  4739.2 1320.80  4745.3 1319.42  4911.0 1313.04
  4982.2 1311.54  4996.9 1306.20  4997.2 1305.70  5000.9 1306.20  5022.6 1310.69
  5033.0 1310.68  5044.6 1312.62  5282.7 1323.82  5303.6 1325.82  5329.6 1325.65
#Mann=3,-1,0
  4373.5    0.05       0  4996.9    0.03       0  5000.9    0.05       0
Bank Sta=4996.9,5000.9
Exp/Cntr=0.3,0.1

Type RM Length L Ch R = 1,9000,500,500,500
BEGIN DESCRIPTION:
SANFERNANDO008 18.0
END DESCRIPTION:
XS GIS Cut Line= 3
      2797755.68     10211503.10      2798279.72     10212018.18
      2798755.71     10211903.10
#Sta/Elev= 30
  4265.2 1338.61  4279.3 1338.08  4286.4 1335.05  4307.6 1330.59  4321.7 1326.41
  4343.0 1322.89  4371.3 1315.82  4427.9 1314.52  4434.9 1312.72  4449.0 1311.08
  4477.3 1310.12  4491.5 1312.23  4576.3 1308.54  4583.4 1307.22  4590.5 1308.02
  4647.0 1306.22  4675.3 1304.35  4696.6 1301.44  4717.7 1300.49  4753.2 1303.61
  4873.3 1300.48  4958.2 1300.13  4998.0 1297.05  4998.2 1296.55  5002.0 1297.05
  5037.0 1300.84  5057.6 1301.98  5160.5 1305.89  5366.2 1315.78  5489.7 1325.75
#Mann=3,-1,0
  4265.2    0.05       0  4998.0    0.03       0  5002.0    0.05       0
Bank Sta=4998,5002
Exp/Cntr=0.3,0.1

Type RM Length L Ch R = 1,8500,500,500,500
BEGIN DESCRIPTION:
SANFERNANDO008 17.0
END DESCRIPTION:
XS GIS Cut Line= 3
      2797505.68     10211853.11      2797981.73     10212353.28
      2798355.68     10212553.11
#Sta/Elev= 30
  4309.5 1359.60  4313.6 1359.37  4323.5 1353.75  4330.7 1352.31  4340.8 1348.00
  4351.8 1345.41  4366.0 1339.35  4387.4 1333.88  4408.4 1326.58  4472.3 1312.57
  4493.3 1312.65  4620.7 1303.89  4804.8 1294.52  4840.0 1293.72  4861.4 1291.66
  4903.5 1290.88  4939.1 1288.79  4960.1 1290.41  4993.7 1287.85  4993.9 1287.35
  4997.7 1287.85  5032.2 1291.94  5076.0 1292.57  5141.9 1295.45  5218.3 1299.96
  5246.0 1300.50  5276.6 1303.31  5289.8 1303.11  5388.2 1309.64  5424.0 1310.36
#Mann=5,-1,0
  4309.5    0.05       0  4313.6    0.12       0  4340.8    0.05       0
  4993.7    0.05       0  4997.7    0.05       0
Bank Sta=4993.7,4997.7
Exp/Cntr=0.3,0.1

Type RM Length L Ch R = 1,8000,500,500,500
BEGIN DESCRIPTION:
SANFERNANDO008 16.0
END DESCRIPTION:
XS GIS Cut Line= 3
      2797305.66     10212203.08      2797679.04     10212691.76
      2798305.70     10212603.11
#Sta/Elev= 30
  4385.0 1311.88  4571.0 1299.51  4726.9 1291.07  4741.4 1291.86  4756.0 1288.90
  4785.0 1287.44  4826.7 1283.51  4834.9 1284.46  4841.2 1283.54  4849.4 1285.34
  4884.8 1283.61  4891.1 1281.86  4899.3 1282.47  4905.6 1281.69  4920.1 1285.60
  4934.7 1283.72  4940.9 1281.58  4970.0 1279.01  4995.7 1278.24  4996.0 1277.74
  4999.7 1278.24  5037.0 1283.46  5047.1 1283.84  5171.1 1286.65  5299.6 1287.15
  5410.7 1292.04  5511.7 1297.34  5582.4 1302.79  5612.7 1306.89  5632.9 1308.05
#Mann=3,-1,0
  4385.0    0.05       0  4995.7    0.05       0  4999.7    0.05       0
Bank Sta=4995.7,4999.7
Exp/Cntr=0.3,0.1

Type RM Length L Ch R = 1,7500,500,500,500
BEGIN DESCRIPTION:
SANFERNANDO008 15.0
END DESCRIPTION:
XS GIS Cut Line= 3
      2797205.70     10212853.12      2797707.74     10213179.86
      2798355.65     10212653.14
#Sta/Elev= 30
  4401.0 1294.68  4459.9 1295.35  4465.9 1294.64  4791.9 1281.88  4936.9 1277.38
  4949.8 1277.96  4979.1 1275.80  4992.2 1272.72  4992.4 1272.22  4996.2 1272.72
  4998.4 1273.66  5003.3 1272.72  5010.2 1273.00  5017.7 1274.64  5032.0 1275.65
  5110.3 1276.90  5209.4 1279.81  5238.2 1279.53  5287.7 1280.53  5308.5 1281.78
  5351.7 1282.49  5394.8 1284.68  5409.1 1284.57  5479.5 1287.26  5720.8 1299.24
  5784.8 1304.19  5792.7 1303.91  5807.0 1304.73  5827.9 1306.79  5835.0 1306.06
#Mann=3,-1,0
  4401.0    0.05       0  4992.2    0.05       0  4996.2    0.05       0
Bank Sta=4992.2,4996.2
Exp/Cntr=0.3,0.1

Type RM Length L Ch R = 1,7000,500,500,500
BEGIN DESCRIPTION:
SANFERNANDO008 14.0
END DESCRIPTION:
XS GIS Cut Line= 3
      2797205.72     10213503.12      2797894.30     10213627.95
      2798305.71     10213103.08
#Sta/Elev= 30
  4300.2 1288.71  4361.1 1289.66  4412.0 1288.82  4472.9 1286.05  4492.3 1286.39
  4550.8 1284.02  4584.7 1284.48  4604.2 1283.02  4667.8 1282.00  4676.2 1280.50
  4706.7 1278.59  4721.3 1278.64  4774.7 1274.74  4859.1 1271.46  4869.3 1271.94
  4886.6 1270.23  4920.1 1269.41  4945.2 1267.15  4968.9 1263.78  4969.2 1263.28
  4972.9 1263.78  4998.2 1267.56  5025.9 1267.33  5040.3 1268.55  5210.3 1272.96
  5303.4 1276.71  5332.4 1279.10  5396.5 1281.02  5638.8 1291.61  5666.9 1294.25
#Mann=3,-1,0
  4300.2    0.05       0  4968.9    0.05       0  4972.9    0.05       0
Bank Sta=4968.9,4972.9
Exp/Cntr=0.3,0.1

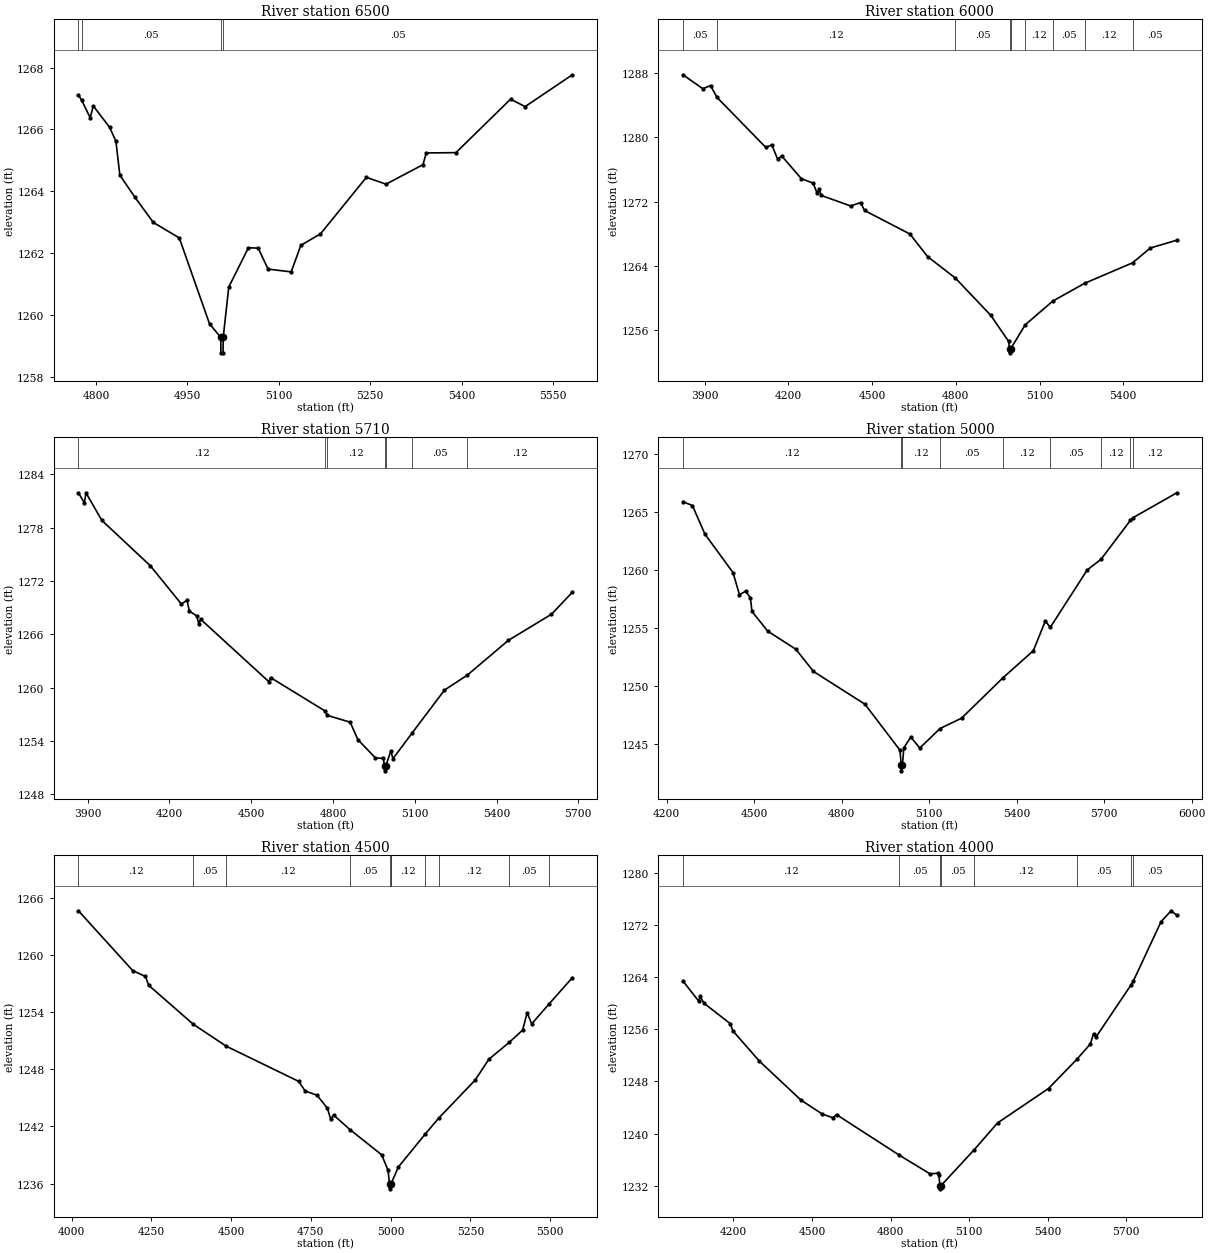
Type RM Length L Ch R = 1,6500,500,500,500
BEGIN DESCRIPTION:
SANFERNANDO008 13.0
END DESCRIPTION:
XS GIS Cut Line= 3
      2798005.67     10213903.11      2798228.98     10213952.49
      2798770.01     10213738.54
#Sta/Elev= 30
  4771.3 1267.12  4776.5 1266.95  4790.6 1266.38  4795.7 1266.76  4822.5 1266.07
  4832.8 1265.62  4839.3 1264.52  4863.5 1263.82  4894.2 1262.99  4936.8 1262.49
  4986.4 1259.71  5004.9 1259.27  5005.1 1258.77  5008.6 1258.77  5008.9 1259.27
  5018.0 1260.90  5050.2 1262.17  5066.3 1262.16  5082.5 1261.48  5120.4 1261.39
  5136.3 1262.25  5168.5 1262.62  5243.8 1264.45  5276.1 1264.23  5336.7 1264.86
  5342.1 1265.24  5390.8 1265.25  5480.4 1266.98  5504.3 1266.74  5581.8 1267.77
#Mann=4,-1,0
  4771.3    0.12       0  4776.5    0.05       0  5004.9    0.03       0
  5008.9    0.05       0
Bank Sta=5004.9,5008.9
Exp/Cntr=0.3,0.1

Type RM Length L Ch R = 1,6000,290,290,290
BEGIN DESCRIPTION:
SANFERNANDO008 12.0
END DESCRIPTION:
XS GIS Cut Line= 3
      2797305.65     10213553.08      2798138.57     10214385.95
      2798730.72     10214378.11
#Sta/Elev= 30
  3822.1 1287.81  3892.9 1286.08  3921.1 1286.46  3944.1 1284.99  4119.1 1278.76
  4140.3 1279.09  4161.6 1277.28  4175.7 1277.71  4246.4 1274.87  4288.8 1274.31
  4303.0 1273.03  4310.1 1273.62  4317.1 1272.79  4423.2 1271.47  4458.5 1271.90
  4472.7 1270.91  4635.3 1267.98  4699.0 1265.16  4798.4 1262.49  4925.2 1257.85
  4988.9 1254.62  4992.5 1253.68  4992.7 1253.18  4996.5 1253.68  5048.8 1256.68
  5147.6 1259.63  5261.7 1261.84  5433.3 1264.39  5497.2 1266.24  5592.2 1267.21
#Mann=9,-1,0
  3822.1    0.05       0  3944.1    0.12       0  4798.4    0.05       0
  4992.5    0.05       0  4996.5    0.05       0  5048.8    0.12       0
  5147.6    0.05       0  5261.7    0.12       0  5433.3    0.05       0
Bank Sta=4992.5,4996.5
Exp/Cntr=0.3,0.1

Type RM Length L Ch R = 1,5710,710,710,710
BEGIN DESCRIPTION:
SANFERNANDO008 11.0
END DESCRIPTION:
XS GIS Cut Line= 3
      2797305.68     10213753.10      2798034.77     10214679.26
      2798655.64     10214803.10
#Sta/Elev= 30
  3866.1 1281.93  3887.8 1280.79  3894.1 1281.91  3951.9 1278.83  4129.9 1273.72
  4243.8 1269.42  4264.6 1269.85  4272.7 1268.63  4299.9 1268.09  4307.9 1267.15
  4314.3 1267.71  4564.5 1260.69  4570.9 1261.15  4770.8 1257.39  4778.9 1256.90
  4862.8 1256.13  4891.7 1254.15  4955.8 1252.11  4984.7 1252.06  4989.1 1251.16
  4989.3 1250.66  4993.1 1251.16  5011.9 1252.88  5020.0 1252.03  5089.3 1254.88
  5208.9 1259.74  5292.9 1261.43  5443.1 1265.33  5601.4 1268.27  5677.9 1270.74
#Mann=7,-1,0
  3866.1    0.12       0  4770.8    0.05       0  4778.9    0.12       0
  4989.1    0.07       0  4993.1    0.12       0  5089.3    0.05       0
  5292.9    0.12       0
Bank Sta=4989.1,4993.1
Exp/Cntr=0.3,0.1

Type RM Length L Ch R = 1,5000,500,500,500
BEGIN DESCRIPTION:
SANFERNANDO008 10.0
END DESCRIPTION:
XS GIS Cut Line= 3
      2797205.68     10214353.10      2797479.41     10215044.81
      2798405.68     10215253.11
#Sta/Elev= 30
  4256.1 1265.85  4288.4 1265.52  4331.4 1263.06  4427.8 1259.74  4449.7 1257.84
  4471.2 1258.15  4487.2 1257.57  4492.7 1256.40  4546.7 1254.70  4643.3 1253.14
  4703.5 1251.23  4879.9 1248.41  5000.0 1244.45  5004.4 1243.17  5004.7 1242.67
  5008.4 1243.17  5013.3 1244.65  5037.2 1245.58  5067.9 1244.63  5137.2 1246.31
  5211.4 1247.21  5353.4 1250.69  5457.4 1253.02  5498.4 1255.58  5515.2 1255.02
  5641.9 1259.97  5689.6 1260.90  5789.9 1264.24  5798.1 1264.46  5949.4 1266.62
#Mann=9,-1,0
  4256.1    0.12       0  5004.4    0.07       0  5008.4    0.12       0
  5137.2    0.05       0  5353.4    0.12       0  5515.2    0.05       0
  5689.6    0.12       0  5789.9    0.05       0  5798.1    0.12       0
Bank Sta=5004.4,5008.4
Exp/Cntr=0.3,0.1

Type RM Length L Ch R = 1,4500,500,500,500
BEGIN DESCRIPTION:
SANFERNANDO008 9.0
END DESCRIPTION:
XS GIS Cut Line= 3
      2797155.68     10214403.11      2797123.11     10215381.16
      2797505.71     10215803.14
#Sta/Elev= 30
  4021.4 1264.62  4191.5 1258.35  4231.5 1257.73  4241.5 1256.81  4381.8 1252.71
  4484.7 1250.42  4711.8 1246.73  4731.8 1245.73  4769.6 1245.27  4801.8 1243.91
  4811.8 1242.80  4821.8 1243.18  4873.4 1241.65  4971.9 1239.03  4991.9 1237.41
  4996.5 1235.96  4996.7 1235.46  5000.5 1235.96  5000.8 1235.96  5024.5 1237.76
  5107.9 1241.18  5150.4 1242.86  5265.1 1246.87  5307.7 1249.04  5372.2 1250.83
  5413.8 1252.11  5428.0 1253.93  5442.2 1252.76  5495.6 1254.81  5569.6 1257.60
#Mann=11,-1,0
  4021.4    0.12       0  4381.8    0.05       0  4484.7    0.12       0
  4873.4    0.05       0  4996.5    0.05       0  5000.5    0.05       0
  5000.8    0.12       0  5107.9    0.05       0  5150.4    0.12       0
  5372.2    0.05       0  5495.6    0.12       0
Bank Sta=4996.5,5000.5
Exp/Cntr=0.3,0.1

Type RM Length L Ch R = 1,4000,500,500,500
BEGIN DESCRIPTION:
SANFERNANDO008 8.0
END DESCRIPTION:
XS GIS Cut Line= 3
      2796555.68     10214403.11      2796631.97     10215392.17
      2797005.68     10216203.10
#Sta/Elev= 30
  4008.0 1263.41  4068.1 1260.33  4073.1 1261.07  4088.2 1260.01  4188.5 1256.87
  4198.3 1255.78  4298.9 1251.15  4458.7 1245.13  4539.6 1243.00  4579.7 1242.43
  4594.0 1242.91  4831.9 1236.73  4950.8 1233.82  4979.6 1233.91  4984.6 1233.57
  4988.9 1232.02  4989.2 1231.52  4992.9 1232.02  5120.0 1237.55  5208.4 1241.63
  5403.0 1246.92  5510.6 1251.38  5562.6 1253.75  5574.7 1255.33  5584.6 1254.84
  5718.3 1262.84  5727.0 1263.44  5832.8 1272.55  5870.9 1274.20  5892.9 1273.50
#Mann=8,-1,0
  4008.0    0.12       0  4831.9    0.05       0  4988.9    0.05       0
  4992.9    0.05       0  5120.0    0.12       0  5510.6    0.05       0
  5718.3    0.12       0  5727.0    0.05       0
Bank Sta=4988.9,4992.9
Exp/Cntr=0.3,0.1

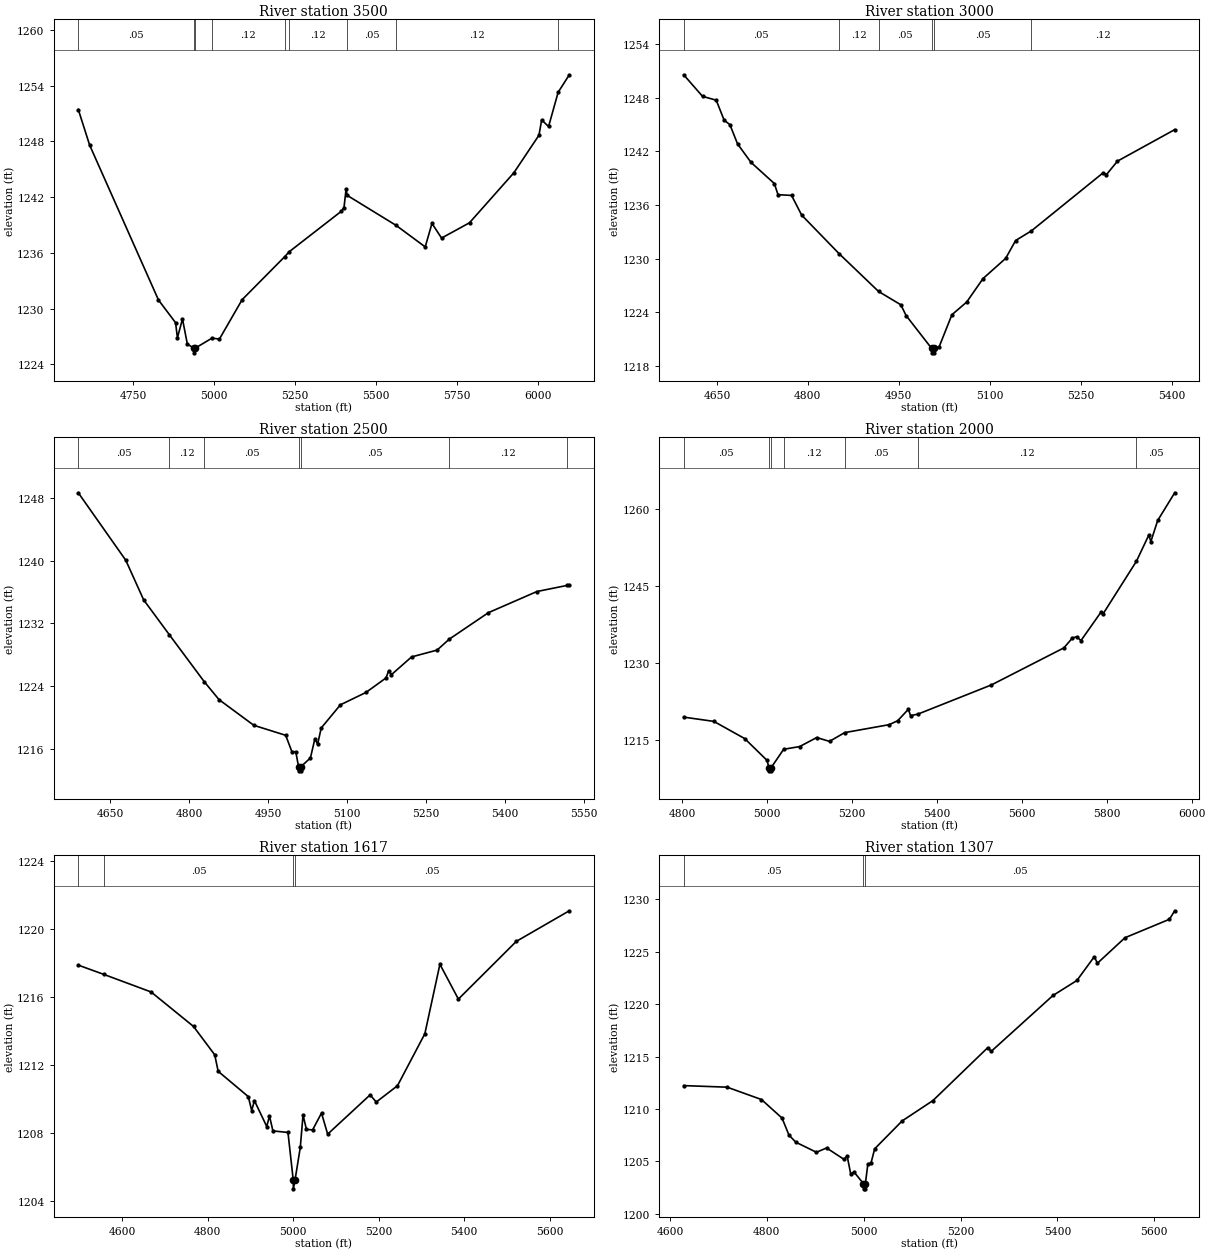
Type RM Length L Ch R = 1,3500,500,500,500
BEGIN DESCRIPTION:
SANFERNANDO008 7.0
END DESCRIPTION:
XS GIS Cut Line= 4
      2795905.72     10214903.13      2796266.41     10215116.36
      2796248.47     10215328.78      2796755.66     10216053.08
#Sta/Elev= 30
  4581.0 1251.44  4616.0 1247.61  4828.7 1230.92  4881.4 1228.48  4887.2 1226.85
  4902.8 1228.88  4917.8 1226.18  4937.9 1225.73  4938.1 1225.23  4941.9 1225.73
  4994.2 1226.82  5016.8 1226.71  5087.1 1230.96  5218.3 1235.58  5232.4 1236.12
  5393.4 1240.48  5401.6 1240.88  5408.2 1242.92  5411.1 1242.20  5562.4 1238.96
  5652.4 1236.64  5673.3 1239.17  5702.9 1237.59  5789.2 1239.24  5926.1 1244.62
  6003.7 1248.67  6012.0 1250.31  6033.4 1249.61  6062.9 1253.29  6097.4 1255.18
#Mann=9,-1,0
  4581.0    0.05       0  4937.9    0.07       0  4941.9    0.05       0
  4994.2    0.12       0  5218.3    0.05       0  5232.4    0.12       0
  5411.1    0.05       0  5562.4    0.12       0  6062.9    0.05       0
Bank Sta=4937.9,4941.9
Exp/Cntr=0.3,0.1

Type RM Length L Ch R = 1,3000,500,500,500
BEGIN DESCRIPTION:
SANFERNANDO008 6.0
END DESCRIPTION:
XS GIS Cut Line= 3
      2795555.67     10215253.11      2795919.85     10215429.86
      2796305.64     10215553.10
#Sta/Elev= 30
  4595.2 1250.54  4626.3 1248.13  4648.9 1247.70  4661.9 1245.47  4671.4 1244.97
  4684.1 1242.81  4706.4 1240.74  4744.7 1238.39  4750.8 1237.14  4773.1 1237.06
  4789.8 1234.86  4851.4 1230.56  4916.6 1226.33  4953.3 1224.84  4962.0 1223.64
  5004.1 1219.97  5004.4 1219.47  5007.9 1219.47  5008.1 1219.97  5016.6 1220.16
  5037.6 1223.73  5061.9 1225.14  5088.9 1227.77  5126.3 1230.03  5142.6 1232.02
  5168.7 1233.10  5287.2 1239.60  5292.4 1239.38  5310.6 1240.89  5405.0 1244.41
#Mann=6,-1,0
  4595.2    0.05       0  4851.4    0.12       0  4916.6    0.05       0
  5004.1    0.05       0  5008.1    0.05       0  5168.7    0.12       0
Bank Sta=5004.1,5008.1
Exp/Cntr=0.3,0.1

Type RM Length L Ch R = 1,2500,500,500,500
BEGIN DESCRIPTION:
SANFERNANDO008 5.0
END DESCRIPTION:
XS GIS Cut Line= 3
      2795455.68     10215453.11      2795646.41     10215817.29
      2796155.67     10215703.12
#Sta/Elev= 30
  4588.9 1248.62  4679.2 1240.03  4713.1 1235.00  4761.6 1230.59  4828.6 1224.56
  4856.3 1222.31  4922.5 1219.04  4983.0 1217.77  4994.8 1215.68  5002.2 1215.68
  5007.5 1213.75  5007.8 1213.25  5011.3 1213.25  5011.5 1213.75  5030.0 1214.89
  5038.5 1217.34  5043.7 1216.64  5050.5 1218.70  5087.0 1221.65  5135.5 1223.22
  5173.5 1225.06  5178.8 1225.98  5184.0 1225.49  5222.2 1227.74  5270.7 1228.61
  5293.8 1230.00  5368.2 1233.37  5460.4 1236.06  5517.2 1236.83  5521.9 1236.86
#Mann=7,-1,0
  4588.9    0.05       0  4761.6    0.12       0  4828.6    0.05       0
  5007.5    0.05       0  5011.5    0.05       0  5293.8    0.12       0
  5517.2    0.05       0
Bank Sta=5007.5,5011.5
Exp/Cntr=0.3,0.1

Type RM Length L Ch R = 1,2000,383,383,383
BEGIN DESCRIPTION:
SANFERNANDO008 4.0
END DESCRIPTION:
XS GIS Cut Line= 3
      2795505.73     10216253.12      2795699.24     10216287.30
      2796655.64     10216203.12
#Sta/Elev= 30
  4803.5 1219.44  4874.5 1218.61  4947.2 1215.26  5000.0 1211.00  5004.5 1209.47
  5004.7 1208.97  5008.2 1208.97  5008.5 1209.47  5039.0 1213.17  5076.7 1213.70
  5116.9 1215.46  5147.0 1214.71  5182.7 1216.42  5287.6 1217.97  5307.6 1218.74
  5332.8 1220.97  5337.8 1219.74  5354.8 1220.01  5528.5 1225.72  5699.1 1232.94
  5719.2 1234.87  5729.3 1235.11  5739.3 1234.36  5786.8 1239.94  5791.8 1239.62
  5870.0 1249.83  5899.0 1254.91  5904.0 1253.67  5920.0 1257.77  5960.1 1263.17
#Mann=7,-1,0
  4803.5    0.05       0  5004.5    0.05       0  5008.5    0.05       0
  5039.0    0.12       0  5182.7    0.05       0  5354.8    0.12       0
  5870.0    0.05       0
Bank Sta=5004.5,5008.5
Exp/Cntr=0.3,0.1

Type RM Length L Ch R = 1,1617,310,310,310
BEGIN DESCRIPTION:
Mapping XS 2799d66f
END DESCRIPTION:
XS GIS Cut Line= 2
      2795264.46     10216224.94      2795983.69     10217119.59
#Sta/Elev= 30
  4497.9 1217.87  4558.1 1217.32  4668.1 1216.29  4767.3 1214.26  4816.9 1212.59
  4824.9 1211.62  4895.3 1210.13  4903.3 1209.31  4909.7 1209.89  4938.5 1208.37
  4944.9 1208.99  4952.9 1208.11  4988.1 1208.02  5000.5 1205.20  5000.7 1204.70
  5004.5 1205.20  5016.9 1207.14  5023.3 1209.04  5031.3 1208.20  5045.7 1208.17
  5066.5 1209.16  5080.9 1207.92  5180.1 1210.23  5194.5 1209.81  5244.1 1210.77
  5308.1 1213.83  5343.3 1217.92  5386.5 1215.87  5522.0 1219.27  5645.8 1221.07
#Mann=4,-1,0
  4497.9    0.12       0  4558.1    0.05       0  5000.5    0.03       0
  5004.5    0.05       0
Bank Sta=5000.5,5004.5
Exp/Cntr=0.3,0.1

Type RM Length L Ch R = 1,1307,445,445,445
BEGIN DESCRIPTION:
Mapping XS fa580bef
END DESCRIPTION:
XS GIS Cut Line= 2
      2795053.58     10216418.21      2795738.90     10217165.02
#Sta/Elev= 30
  4628.4 1212.24  4718.1 1212.09  4789.0 1210.91  4831.5 1209.14  4845.7 1207.52
  4859.9 1206.84  4902.4 1205.88  4923.4 1206.29  4959.1 1205.21  4965.9 1205.51
  4973.3 1203.79  4980.1 1203.99  4999.5 1202.89  4999.8 1202.39  5003.3 1202.39
  5003.5 1202.89  5008.5 1204.72  5015.3 1204.89  5022.7 1206.21  5079.4 1208.87
  5142.9 1210.81  5256.3 1215.87  5263.1 1215.50  5390.8 1220.84  5440.1 1222.27
  5475.9 1224.53  5482.6 1223.92  5539.4 1226.35  5631.2 1228.11  5642.0 1228.92
#Mann=3,-1,0
  4628.4    0.05       0  4999.5    0.03       0  5003.5    0.05       0
Bank Sta=4999.5,5003.5
Exp/Cntr=0.3,0.1

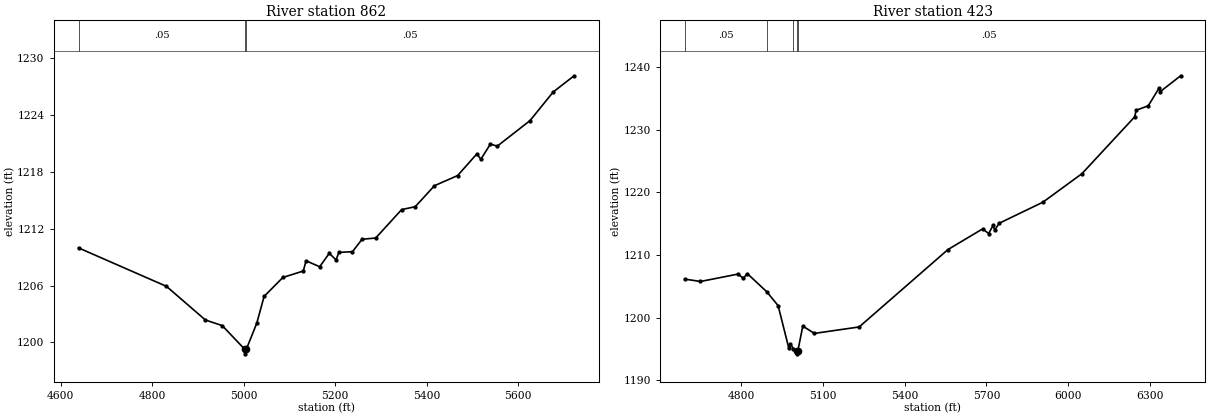
Type RM Length L Ch R = 1,862,439,439,439
BEGIN DESCRIPTION:
Mapping XS 68b62236
END DESCRIPTION:
XS GIS Cut Line= 3
      2794929.62     10216363.75      2794851.50     10216797.74
      2795380.89     10217162.24
#Sta/Elev= 30
  4638.7 1209.97  4831.1 1205.91  4916.2 1202.36  4953.0 1201.77  5001.8 1199.29
  5002.1 1198.79  5005.8 1199.29  5028.5 1202.02  5044.5 1204.85  5085.6 1206.85
  5130.2 1207.53  5136.3 1208.61  5166.1 1207.98  5187.0 1209.40  5201.9 1208.70
  5208.0 1209.49  5237.8 1209.57  5258.7 1210.88  5288.5 1211.01  5345.3 1214.01
  5375.1 1214.32  5417.0 1216.53  5467.7 1217.60  5509.7 1219.89  5518.5 1219.32
  5539.4 1220.93  5554.3 1220.70  5626.0 1223.40  5676.7 1226.42  5722.4 1228.13
#Mann=3,-1,0
  4638.7    0.05       0  5001.8    0.03       0  5005.8    0.05       0
Bank Sta=5001.8,5005.8
Exp/Cntr=0.3,0.1

Type RM Length L Ch R = 1,423,0,0,0
BEGIN DESCRIPTION:
SANFERNANDO008 1.0
END DESCRIPTION:
XS GIS Cut Line= 4
      2794680.69     10216328.10      2794486.92     10216476.56
      2794443.51     10216849.82      2795505.66     10217403.10
#Sta/Elev= 30
  4594.7 1206.16  4651.4 1205.79  4787.9 1206.96  4808.7 1206.32  4823.2 1207.04
  4893.9 1204.17  4936.0 1201.94  4975.3 1195.14  4980.3 1195.85  4992.3 1195.06
  5004.5 1194.74  5004.7 1194.24  5008.5 1194.74  5026.6 1198.67  5068.9 1197.50
  5233.2 1198.53  5559.1 1210.89  5686.0 1214.18  5708.1 1213.44  5724.4 1214.74
  5730.2 1213.98  5746.7 1215.08  5907.0 1218.44  6050.4 1223.00  6243.1 1232.04
  6249.3 1233.12  6293.5 1233.83  6332.1 1236.59  6337.7 1236.10  6412.2 1238.62
#Mann=5,-1,0
  4594.7    0.05       0  4893.9    0.12       0  4992.3    0.05       0
  5004.5    0.05       0  5008.5    0.05       0
Bank Sta=5004.5,5008.5
Exp/Cntr=0.3,0.1

Chan Stop Cuts=-1