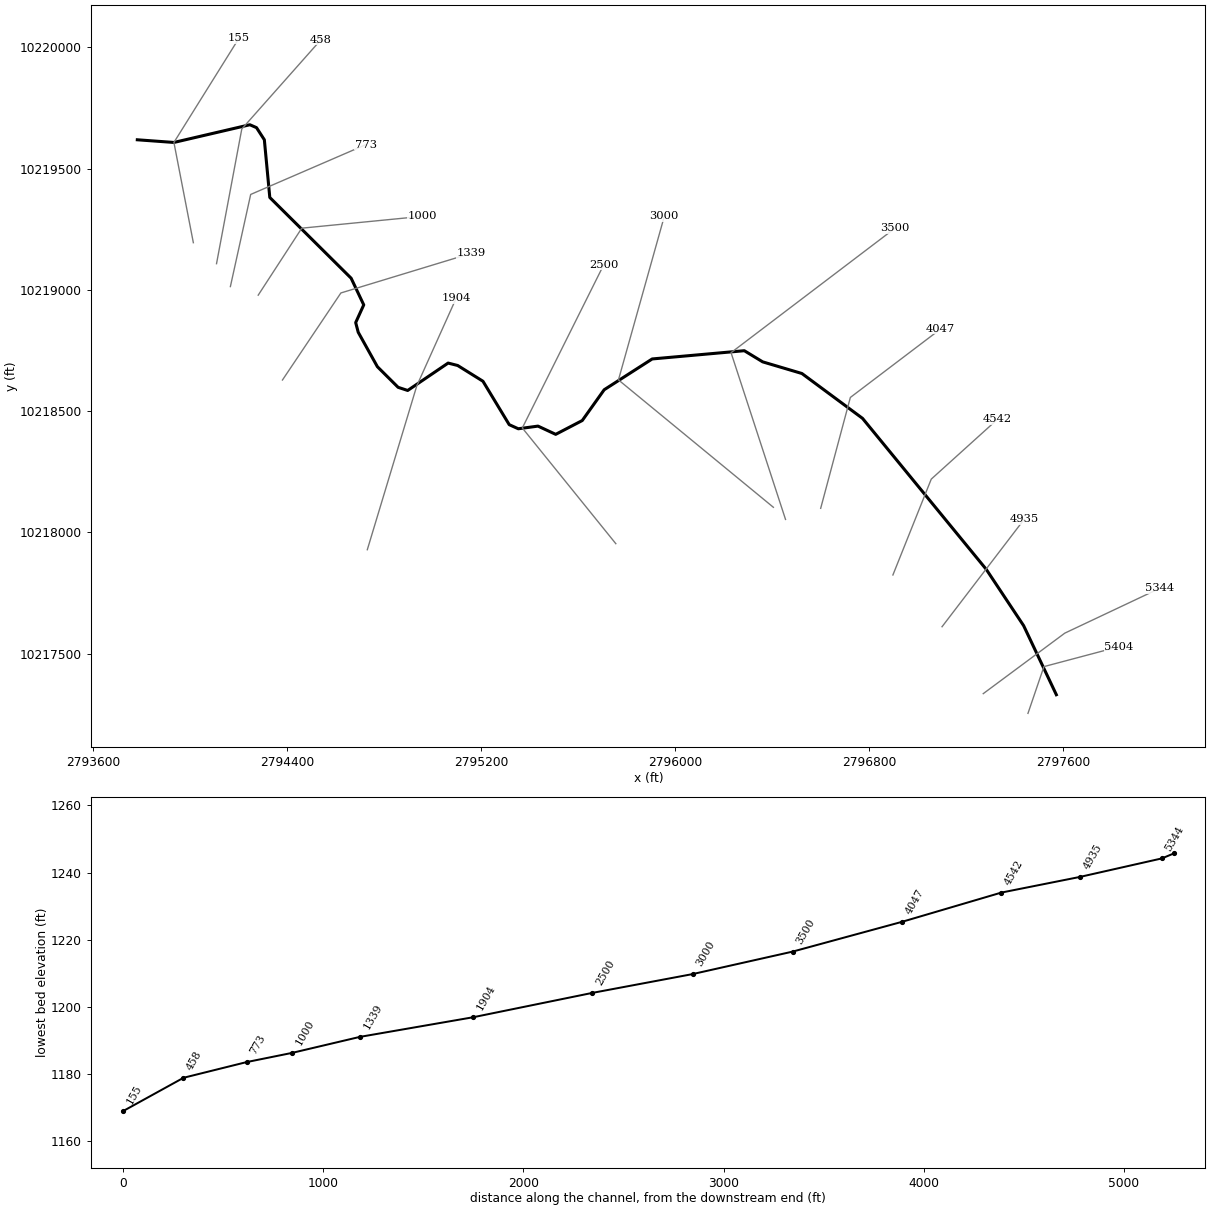
--- SANFERNANDO009.prj (project) ---

Proj Title=SANFERNANDO009 Base Level Engineering
Current Plan=p01
Default Exp/Contr=0.3,0.1
English Units
Geom File=g01
Flow File=f01
Plan File=p01
Y Axis Title=Elevation
X Axis Title(PF)=Main Channel Distance
X Axis Title(XS)=Station
BEGIN DESCRIPTION:
SANFERNANDO009
END DESCRIPTION:
DSS Export Rating Curves= 0
DSS Export Rating Curve Sorted= 0
DSS Export Volume Flow Curves= 0
DXF OffsetX= 0
DXF OffsetY= 0
DXF ScaleX= 1
DXF ScaleY= 10

--- SANFERNANDO009.p01 (plan) ---

Plan Title=Multiple Run
Short Identifier=Multiple
Geom File=g01
Flow File=f01
Subcritical Flow
K Sum by GR= 0
Std Step Tol= 0.01
Critical Tol= 0.01
Num of Std Step Trials= 20
Max Error Tol= 0.3
Flow Tol Ratio= 0.001
Split Flow NTrial= 30
Split Flow Tol= 0.02
Split Flow Ratio= 0.02
Log Output Level= 0
Friction Slope Method= 1
Unsteady Friction Slope Method= 2
Unsteady Bridges Friction Slope Method= 1
Parabolic Critical Depth
Global Vel Dist=  1 , 1 , 1
Global Log Level= 0
CheckData=True
Encroach Param= -1, 0, 0, 0
BEGIN DESCRIPTION:
Multiple Run
END DESCRIPTION:

--- SANFERNANDO009.f01 (steady flow) ---

Flow Title=Multiple
Number of Profiles=7
Profile Names=10-year,25-year,50-year,1pct_min,100-year,1pct_plu,500-year
River Rch & RM= SANFERNANDO009,Reach-1,5404
     183     282     322     207     413     825     569
Boundary for River Rch & Prof#=SANFERNANDO009,Reach-1,1
Up Type=0
Dn Type=3
Dn Slope=0.005
Boundary for River Rch & Prof#=SANFERNANDO009,Reach-1,2
Up Type=0
Dn Type=3
Dn Slope=0.005
Boundary for River Rch & Prof#=SANFERNANDO009,Reach-1,3
Up Type=0
Dn Type=3
Dn Slope=0.005
Boundary for River Rch & Prof#=SANFERNANDO009,Reach-1,4
Up Type=0
Dn Type=3
Dn Slope=0.005
Boundary for River Rch & Prof#=SANFERNANDO009,Reach-1,5
Up Type=0
Dn Type=3
Dn Slope=0.005
Boundary for River Rch & Prof#=SANFERNANDO009,Reach-1,6
Up Type=0
Dn Type=3
Dn Slope=0.005
Boundary for River Rch & Prof#=SANFERNANDO009,Reach-1,7
Up Type=0
Dn Type=3
Dn Slope=0.005

--- SANFERNANDO009.g01 (geometry) ---

Geom Title=Existing Conditions
Program Version=4.10

River Reach=SANFERNANDO009  ,Reach-1
Reach XY= 30
      2797572.75       10217330.      2797437.75       10217615.
      2797283.75       10217847.      2796773.25       10218470.
      2796523.25       10218655.       2796361.5       10218703.
      2796285.75       10218749.      2795905.75       10218715.
      2795707.75       10218588.      2795617.25       10218461.
      2795507.75       10218404.      2795434.75       10218438.
       2795353.5       10218427.        2795316.       10218444.
      2795207.75       10218623.       2795103.5       10218688.
        2795064.       10218698.      2794897.25       10218585.
      2794857.75       10218598.      2794772.25       10218683.
      2794693.25       10218825.      2794682.75       10218865.
        2794716.       10218938.        2794664.       10219048.
       2794328.5       10219381.        2794306.       10219619.
      2794273.75       10219669.      2794246.25       10219681.
        2793933.       10219608.        2793782.       10219619.

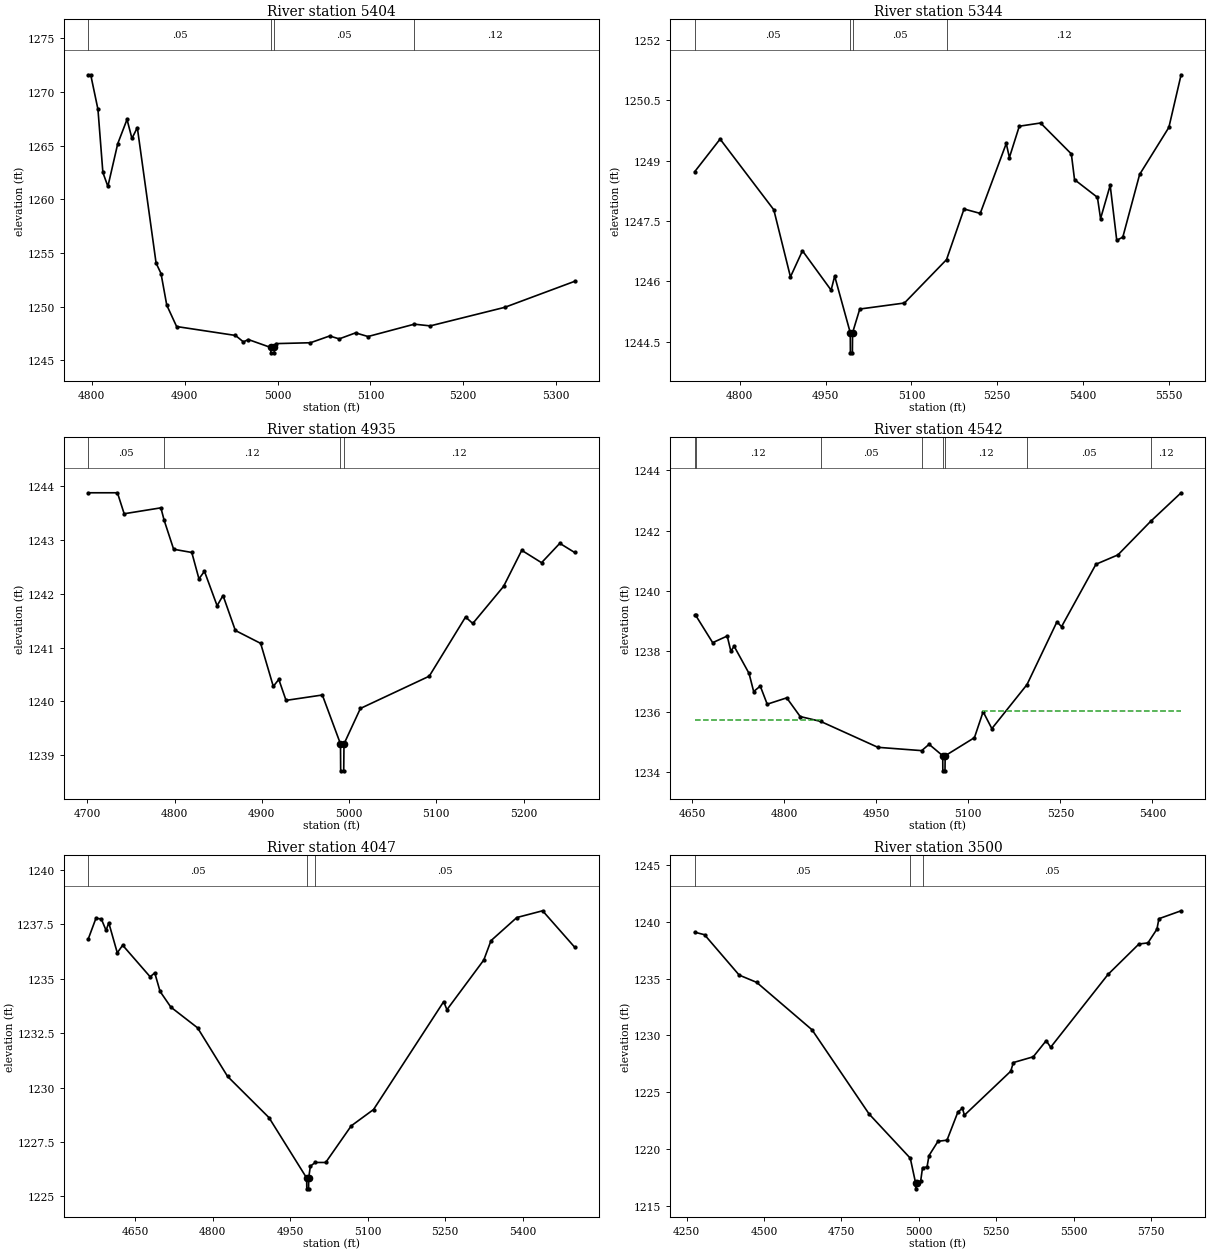
Type RM Length L Ch R = 1 ,5404    ,60,60,60
BEGIN DESCRIPTION:
SANFERNANDO009 11.0
END DESCRIPTION:
XS GIS Cut Line= 3
      2797455.69     10217253.12       2797521.5       10217446.
      2797830.68     10217528.11
#Sta/Elev= 30
  4796.2 1271.61  4798.8 1271.61  4806.6 1268.39  4811.9 1262.51  4817.3 1261.21
  4827.9 1265.19  4837.9 1267.45  4843.2 1265.68    4849 1266.69  4869.2 1254.07
  4874.5  1253.1  4880.7 1250.15  4891.3 1248.16  4954.7 1247.33  4963.2 1246.73
  4968.5 1246.95  4992.6 1246.21  4992.8 1245.71  4996.3 1245.71  4996.6 1246.21
  4998.7 1246.57  5035.4 1246.65  5056.1 1247.28  5066.4 1247.01    5084 1247.57
  5097.4 1247.23  5147.3 1248.38  5164.4 1248.22  5244.7 1249.95  5319.9 1252.37
#Mann= 4 ,-1 , 0
  4796.2     .05       0  4992.6     .05       0  4996.6     .05       0
  5147.3     .12       0
Bank Sta=4992.6,4996.6
XS Rating Curve= 0 ,0
Exp/Cntr=0.3,0.1

Type RM Length L Ch R = 1 ,5344    ,409,409,409
BEGIN DESCRIPTION:
Mapping XS 31165c67
END DESCRIPTION:
XS GIS Cut Line= 3
       2797271.3     10217334.53      2797607.63     10217584.07
      2797997.82     10217768.32
#Sta/Elev= 30
  4721.2 1248.73  4765.5 1249.54  4859.4 1247.78  4888.5 1246.11  4909.5 1246.76
  4959.6 1245.78  4965.8 1246.13  4993.1 1244.72  4993.3 1244.22  4996.8 1244.22
  4997.1 1244.72  5009.7 1245.31  5087.8 1245.46  5161.4 1246.54    5192  1247.8
  5220.3 1247.69  5265.8 1249.43  5271.3 1249.08  5288.6 1249.86  5325.8 1249.94
  5379.6 1249.17  5385.2 1248.53  5425.2 1248.09  5430.7 1247.56  5447.5 1248.39
    5459 1247.02  5469.6  1247.1    5499 1248.66  5550.1 1249.83  5571.5 1251.14
#Mann= 4 ,-1 , 0
  4721.2     .05       0  4993.1     .05       0  4997.1     .05       0
  5161.4     .12       0
Bank Sta=4993.1,4997.1
XS Rating Curve= 0 ,0
Exp/Cntr=0.3,0.1

Type RM Length L Ch R = 1 ,4935    ,393,393,393
BEGIN DESCRIPTION:
Mapping XS e29f3445
END DESCRIPTION:
XS GIS Cut Line= 2
      2797101.27     10217610.49       2797439.8     10218053.18
#Sta/Elev= 30
  4701.2 1243.88  4734.6 1243.88  4742.3 1243.49  4784.4  1243.6  4788.1 1243.37
    4799 1242.83  4819.8 1242.77    4828 1242.28  4834.3 1242.42  4848.8 1241.78
  4855.6 1241.97  4869.7 1241.32  4898.7 1241.08  4913.2 1240.28  4919.5 1240.41
  4927.8 1240.02  4969.4 1240.12  4990.2 1239.21  4990.4 1238.71  4993.9 1238.71
  4994.2 1239.21    5013 1239.87  5091.9 1240.47  5133.5 1241.57  5141.8 1241.45
  5177.1 1242.14  5197.9 1242.81  5220.6 1242.58  5241.5 1242.94  5258.5 1242.77
#Mann= 4 ,-1 , 0
  4701.2     .05       0  4788.1     .12       0  4990.2     .07       0
  4994.2     .12       0
Bank Sta=4990.2,4994.2
XS Rating Curve= 0 ,0
Exp/Cntr=0.3,0.1

Type RM Length L Ch R = 1 ,4542    ,495,495,495
BEGIN DESCRIPTION:
Mapping XS d48c3242
END DESCRIPTION:
XS GIS Cut Line= 3
      2796898.63     10217823.97      2797056.77     10218219.32
      2797329.12     10218465.31
#Sta/Elev= 30
  4654.1  1239.2  4655.5  1239.2  4683.3 1238.29    4707 1238.51  4712.9 1238.01
  4718.3 1238.17  4742.6 1237.27  4750.1 1236.67  4760.9 1236.85  4772.2 1236.25
    4804 1236.46    4826 1235.84  4859.2 1235.68  4952.6 1234.82    5024 1234.71
  5036.1 1234.92  5058.3 1234.54  5058.5 1234.04    5062 1234.04  5062.3 1234.54
    5110 1235.14  5124.2    1236  5138.4 1235.44  5195.7  1236.9  5244.5 1238.98
    5252 1238.82  5308.1 1240.89  5343.9  1241.2  5397.1 1242.31  5446.9 1243.26
#Mann= 8 ,-1 , 0
  4654.1     .05       0  4655.5     .12       0  4859.2     .05       0
    5024     .12       0  5058.3     .05       0  5062.3     .12       0
  5195.7     .05       0  5397.1     .12       0
#XS Ineff= 2 , 0
         4858.52 1235.74 5124.43         1236.02
Permanent Ineff=
       F       F
Bank Sta=5058.3,5062.3
XS Rating Curve= 0 ,0
Exp/Cntr=0.3,0.1

Type RM Length L Ch R = 1 ,4047    ,547,547,547
BEGIN DESCRIPTION:
Mapping XS 28f00012
END DESCRIPTION:
XS GIS Cut Line= 3
      2796600.71     10218098.91      2796723.09      10218556.2
      2797095.72     10218838.88
#Sta/Elev= 30
  4559.6 1236.82  4574.3 1237.76  4584.7 1237.74    4594 1237.21  4599.2 1237.56
  4615.7 1236.18  4626.1 1236.53  4679.3 1235.08  4688.2 1235.26  4698.5 1234.41
  4719.3 1233.69    4771 1232.74  4829.1 1230.51  4909.2 1228.62  4982.1 1225.85
  4982.4 1225.35  4985.9 1225.35  4986.1 1225.85  4989.3 1226.39  4998.7 1226.56
    5019 1226.56  5068.4 1228.24  5111.6 1228.99  5247.3 1233.94  5253.6 1233.57
  5324.9 1235.85  5338.9 1236.74  5388.8  1237.8  5438.7 1238.11  5500.7 1236.44
#Mann= 3 ,-1 , 0
  4559.6     .05       0  4982.1     .05       0  4998.7     .05       0
Bank Sta=4982.1,4986.1
XS Rating Curve= 0 ,0
Exp/Cntr=0.3,0.1

Type RM Length L Ch R = 1 ,3500    ,500,500,500
BEGIN DESCRIPTION:
SANFERNANDO009 7.0
END DESCRIPTION:
XS GIS Cut Line= 3
      2796455.68     10218053.12      2796231.03     10218740.86
      2796905.69     10219253.12
#Sta/Elev= 30
  4276.5 1239.09    4308 1238.87    4420 1235.31  4476.4 1234.67  4655.2 1230.49
  4839.7 1223.06  4972.5 1219.17  4989.8 1216.97  4990.1 1216.47  4993.8 1216.97
    5006 1217.15  5012.1 1218.33  5026.6 1218.39  5032.9  1219.4    5062 1220.66
  5091.1 1220.76  5126.4 1223.25    5141 1223.57  5147.3 1222.96    5297 1226.84
  5305.3  1227.6  5369.7 1228.11  5411.4 1229.53  5425.9 1228.95  5611.1 1235.37
  5710.9 1238.05    5740 1238.15  5769.1 1239.36  5775.4 1240.28  5847.1 1240.98
#Mann= 3 ,-1 , 0
  4276.5     .05       0  4972.5     .05       0  5012.1     .05       0
Bank Sta=4989.8,4993.8
XS Rating Curve= 0 ,0
Exp/Cntr=0.3,0.1

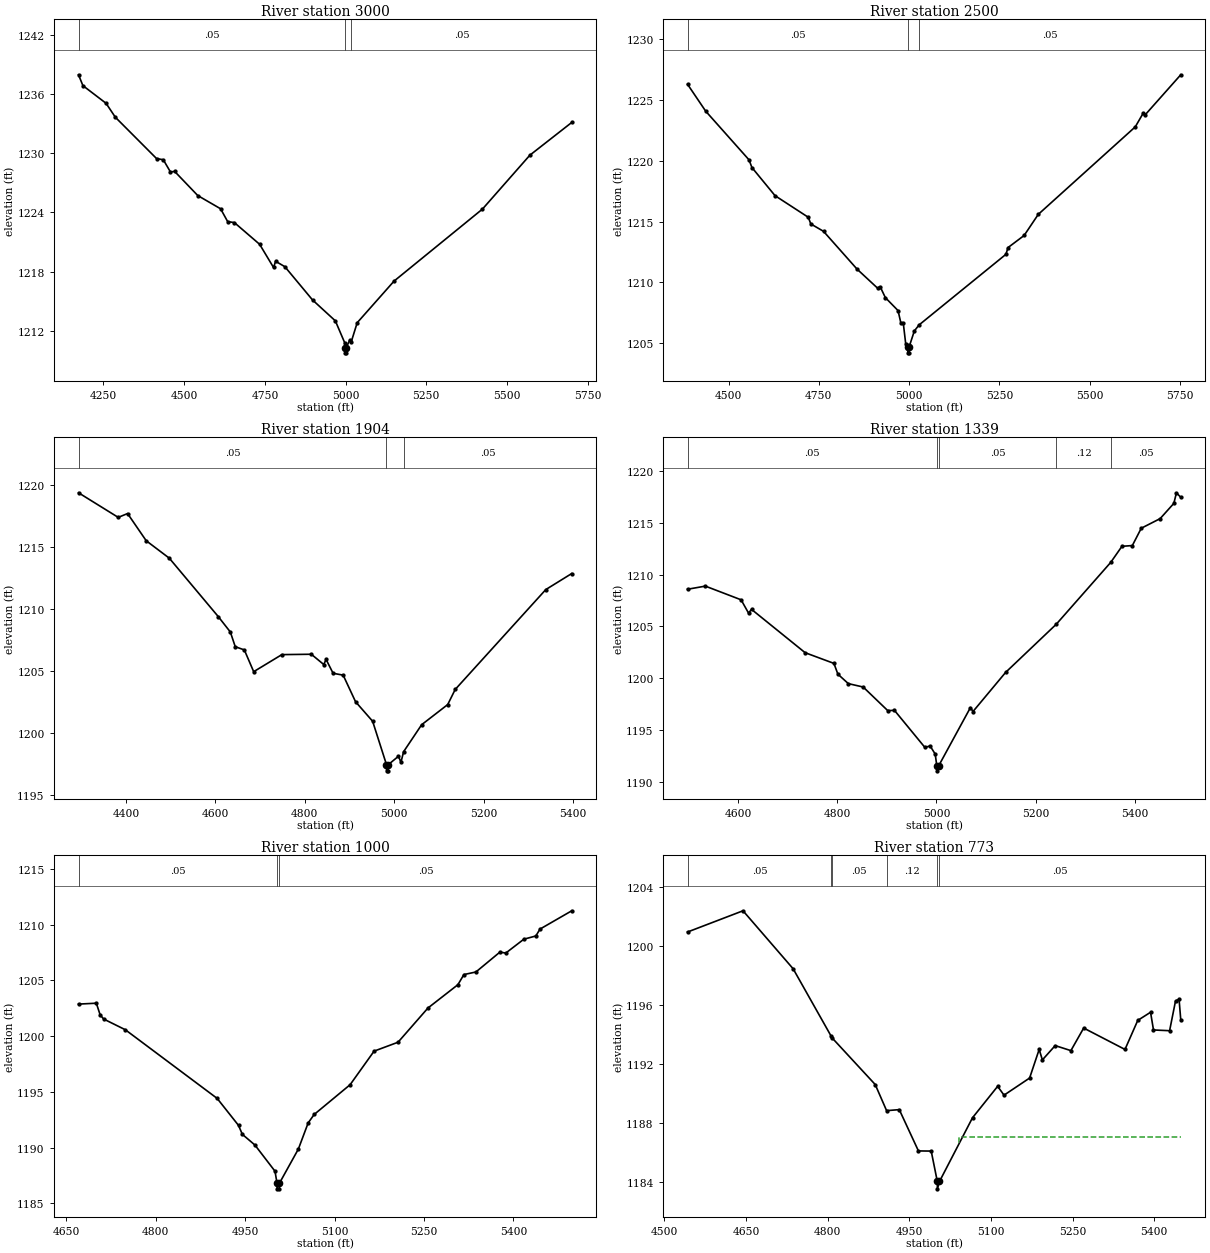
Type RM Length L Ch R = 1 ,3000    ,500,500,500
BEGIN DESCRIPTION:
SANFERNANDO009 6.0
END DESCRIPTION:
XS GIS Cut Line= 3
      2796405.65     10218103.14      2795766.61     10218628.56
       2795955.7     10219303.16
#Sta/Elev= 30
  4172.7 1237.95  4186.3 1236.85    4258 1235.06  4286.7 1233.65  4414.4 1229.46
  4435.3 1229.34  4457.5  1228.1  4470.4 1228.16  4542.1 1225.71  4612.8 1224.37
  4634.7 1223.07  4655.5 1222.97  4733.7 1220.77  4776.8 1218.42  4783.2 1219.05
  4811.9  1218.5  4897.6 1215.13  4968.3 1213.01    4997 1210.81  4997.7 1210.27
  4997.9 1209.77  5001.4 1209.77  5001.7 1210.27  5012.5 1211.04  5017.7  1210.9
  5035.9 1212.82  5150.1 1217.04    5424 1224.34  5570.8  1229.8  5700.6 1233.12
#Mann= 3 ,-1 , 0
  4172.7     .05       0  4997.7     .05       0  5017.7     .05       0
Bank Sta=4997.7,5001.7
XS Rating Curve= 0 ,0
Exp/Cntr=0.3,0.1

Type RM Length L Ch R = 1 ,2500    ,596,596,596
BEGIN DESCRIPTION:
SANFERNANDO009 5.0
END DESCRIPTION:
XS GIS Cut Line= 3
       2795755.7     10217953.09      2795370.03     10218430.33
       2795705.7     10219103.14
#Sta/Elev= 30
  4386.4 1226.31  4436.8 1224.09  4556.7 1220.08  4564.7 1219.45  4628.7 1217.13
  4720.7 1215.35  4727.8  1214.8    4763 1214.19  4855.7 1211.08  4913.3 1209.49
  4919.7 1209.63  4934.1 1208.73  4969.3 1207.66  4977.2 1206.62  4983.7 1206.64
  4990.7 1204.87  4996.1 1204.68  4996.3 1204.18  4999.8 1204.18  5000.1 1204.68
  5014.3 1205.98  5027.5 1206.48    5268  1212.3  5273.6 1212.85  5318.3 1213.85
  5357.5 1215.59    5626  1222.8  5648.4 1223.95    5654 1223.81  5751.9 1227.09
#Mann= 3 ,-1 , 0
  4386.4     .05       0  4996.1     .05       0  5027.5     .05       0
Bank Sta=4996.1,5000.1
XS Rating Curve= 0 ,0
Exp/Cntr=0.3,0.1

Type RM Length L Ch R = 1 ,1904    ,565,565,565
BEGIN DESCRIPTION:
SANFERNANDO009 4.0
END DESCRIPTION:
XS GIS Cut Line= 3
      2794730.69     10217928.13      2794934.75       10218604.
      2795097.52      10218966.1
#Sta/Elev= 30
    4294 1219.41  4382.8 1217.42  4403.7 1217.73  4445.4 1215.53    4497 1214.12
  4606.4  1209.4  4633.5 1208.15  4644.5 1206.96  4664.8  1206.7  4685.7 1204.94
  4748.7 1206.32  4814.6 1206.35  4842.4 1205.52  4847.6 1205.93  4863.3 1204.81
  4885.8 1204.66  4913.5 1202.51  4951.7 1200.93  4982.7 1197.42  4982.9 1196.92
  4986.4 1196.92  4986.7 1197.42  5009.5  1198.1    5015 1197.61    5021 1198.47
  5061.3 1200.65  5119.6 1202.28  5136.3  1203.5  5338.9 1211.58    5397 1212.88
#Mann= 3 ,-1 , 0
    4294     .05       0  4982.7     .05       0    5021     .05       0
Bank Sta=4982.7,4986.7
XS Rating Curve= 0 ,0
Exp/Cntr=0.3,0.1

Type RM Length L Ch R = 1 ,1339    ,339,339,339
BEGIN DESCRIPTION:
SANFERNANDO009 3.0
END DESCRIPTION:
XS GIS Cut Line= 3
      2794380.69     10218628.12      2794621.71     10218987.21
      2795159.03     10219150.62
#Sta/Elev= 30
  4498.2 1208.59  4534.2 1208.89  4606.2 1207.57  4621.2 1206.29  4627.2 1206.65
  4735.3 1202.47  4793.3 1201.44  4801.3  1200.4  4822.3 1199.49  4852.3 1199.16
  4901.7 1196.89  4915.3 1196.91  4976.6 1193.34  4987.1 1193.48  4997.4  1192.7
  5000.6 1191.58  5000.9 1191.08  5004.6 1191.58  5068.4 1197.18  5073.6  1196.8
  5139.3 1200.57  5241.3 1205.21  5351.2 1211.18  5373.8 1212.73  5394.7  1212.8
  5412.7 1214.47  5450.8  1215.4  5478.4 1216.87  5483.6 1217.89  5492.3 1217.45
#Mann= 5 ,-1 , 0
  4498.2     .05       0  5000.6     .05       0  5004.6     .05       0
  5241.3     .12       0  5351.2     .05       0
Bank Sta=5000.6,5004.6
XS Rating Curve= 0 ,0
Exp/Cntr=0.3,0.1

Type RM Length L Ch R = 1 ,1000    ,227,227,227
BEGIN DESCRIPTION:
SANFERNANDO009 2.0
END DESCRIPTION:
XS GIS Cut Line= 3
      2794280.66     10218978.08      2794460.31     10219254.42
      2794955.73     10219303.12
#Sta/Elev= 30
  4670.4 1202.88  4700.3 1202.96  4706.7 1201.91  4712.6 1201.54  4748.9 1200.58
    4903 1194.42  4938.8    1192  4945.2  1191.2  4966.3 1190.24    5000 1187.89
  5003.4 1186.81  5003.6 1186.31  5007.1 1186.31  5007.4 1186.81  5039.2 1189.88
  5055.6 1192.22  5065.7 1192.98    5126 1195.65  5166.2 1198.66  5206.4 1199.46
  5256.6 1202.53  5306.8 1204.62  5316.9 1205.53    5337 1205.76  5377.2 1207.54
  5387.2 1207.46  5417.4  1208.7  5437.5 1208.99  5444.6 1209.61  5497.8 1211.25
#Mann= 3 ,-1 , 0
  4670.4     .05       0  5003.4     .05       0  5007.4     .05       0
Bank Sta=5003.4,5007.4
XS Rating Curve= 0 ,0
Exp/Cntr=0.3,0.1

Type RM Length L Ch R = 1 ,773     ,315,315,315
BEGIN DESCRIPTION:
Mapping XS 733b4a05
END DESCRIPTION:
XS GIS Cut Line= 3
      2794165.92     10219013.51      2794249.66     10219393.55
      2794724.51     10219598.89
#Sta/Elev= 30
  4542.3 1200.98  4644.3 1202.42  4736.4 1198.49  4806.6  1193.9  4808.1  1193.8
  4887.3 1190.64  4908.2 1188.87  4931.5 1188.94  4966.7 1186.14  4990.2 1186.13
  5001.4 1184.07  5001.6 1183.57  5005.4 1184.07  5066.1 1188.39  5112.3 1190.52
    5124 1189.92    5171 1191.08  5188.6 1193.02  5194.5 1192.31    5218 1193.28
  5246.9 1192.94  5270.4 1194.47  5346.3 1193.02  5369.8 1194.99  5393.3 1195.54
  5398.7 1194.34  5428.3 1194.29  5439.2 1196.31  5445.7 1196.42  5448.8 1195.04
#Mann= 6 ,-1 , 0
  4542.3     .05       0  4806.6     .12       0  4808.1     .05       0
  4908.2     .12       0  5001.4     .07       0  5005.4     .05       0
#XS Ineff= 2 , 0
                         5041.59         1187.08
Permanent Ineff=
       F       F
Bank Sta=5001.4,5005.4
XS Rating Curve= 0 ,0
Exp/Cntr=0.3,0.1

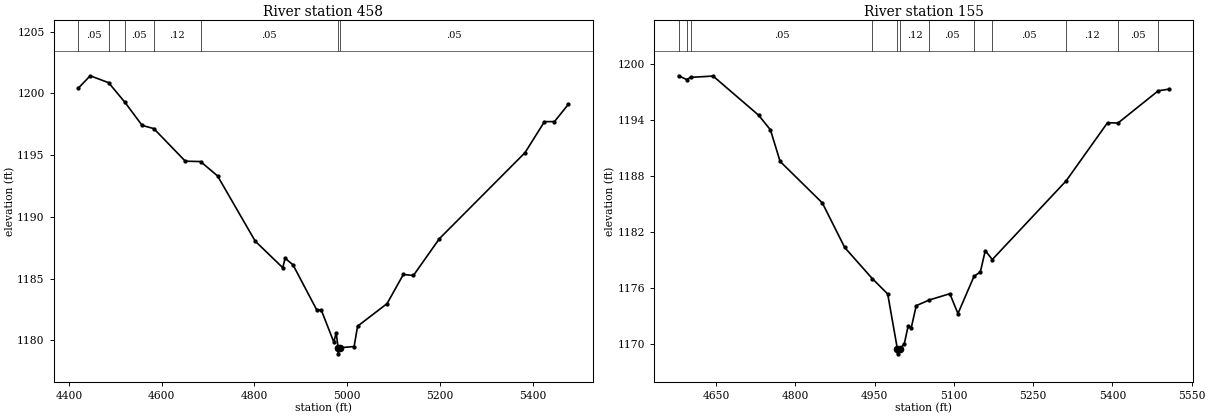
Type RM Length L Ch R = 1 ,458     ,303,303,303
BEGIN DESCRIPTION:
Mapping XS dd92e398
END DESCRIPTION:
XS GIS Cut Line= 3
      2794108.76     10219107.91      2794212.93     10219663.46
      2794539.34     10220031.54
#Sta/Elev= 30
  4419.9 1200.43  4445.5 1201.43  4485.2 1200.87  4520.2 1199.29  4557.5 1197.41
  4582.8 1197.15  4650.7 1194.51  4683.6 1194.48  4720.2 1193.32  4801.6 1188.03
    4861 1185.88  4866.1 1186.64    4883 1186.12  4933.9 1182.49  4944.1 1182.45
  4971.2 1179.85  4976.3 1180.61  4980.4  1179.4  4980.7  1178.9  4984.4  1179.4
    5015 1179.49  5022.5 1181.14  5086.1 1182.97  5121.2 1185.33    5143 1185.25
    5199 1188.23  5383.8  1195.2  5425.7 1197.71  5447.4 1197.72  5477.1 1199.11
#Mann= 7 ,-1 , 0
  4419.9     .05       0  4485.2     .12       0  4520.2     .05       0
  4582.8     .12       0  4683.6     .05       0  4980.4     .05       0
  4984.4     .05       0
Bank Sta=4980.4,4984.4
XS Rating Curve= 0 ,0
Exp/Cntr=0.3,0.1

Type RM Length L Ch R = 1 ,155     ,0,0,0
BEGIN DESCRIPTION:
SANFERNANDO009 1.0
END DESCRIPTION:
XS GIS Cut Line= 3
      2794013.17      10219194.5        2793933.       10219608.
      2794201.01     10220037.43
#Sta/Elev= 30
  4578.8 1198.72  4594.2 1198.31  4601.3 1198.55    4644 1198.69  4730.2  1194.5
  4752.6 1192.93  4770.9 1189.55  4850.9  1185.1  4893.2 1180.33  4945.4    1177
  4974.6 1175.35    4993 1169.44  4993.2 1168.94    4997 1169.44    5006 1170.01
  5013.2  1171.9  5019.1 1171.71  5028.6  1174.1  5053.5 1174.71  5092.2 1175.38
  5107.6 1173.25  5137.9 1177.23    5150 1177.72  5159.3 1179.99  5172.6 1179.04
  5312.3 1187.46  5390.7 1193.69  5410.6 1193.66  5486.7 1197.11  5506.2 1197.28
#Mann= 12 ,-1 , 0
  4578.8     .05       0  4594.2     .12       0  4601.3     .05       0
  4945.4     .12       0    4993     .07       0    4997     .12       0
  5053.5     .05       0  5137.9     .12       0  5172.6     .05       0
  5312.3     .12       0  5410.6     .05       0  5486.7     .12       0
Bank Sta=4993,4997
XS Rating Curve= 0 ,0
Exp/Cntr=0.3,0.1

Chan Stop Cuts=-1
Use User Specified Reach Order=0
Composite Channel Slope=5