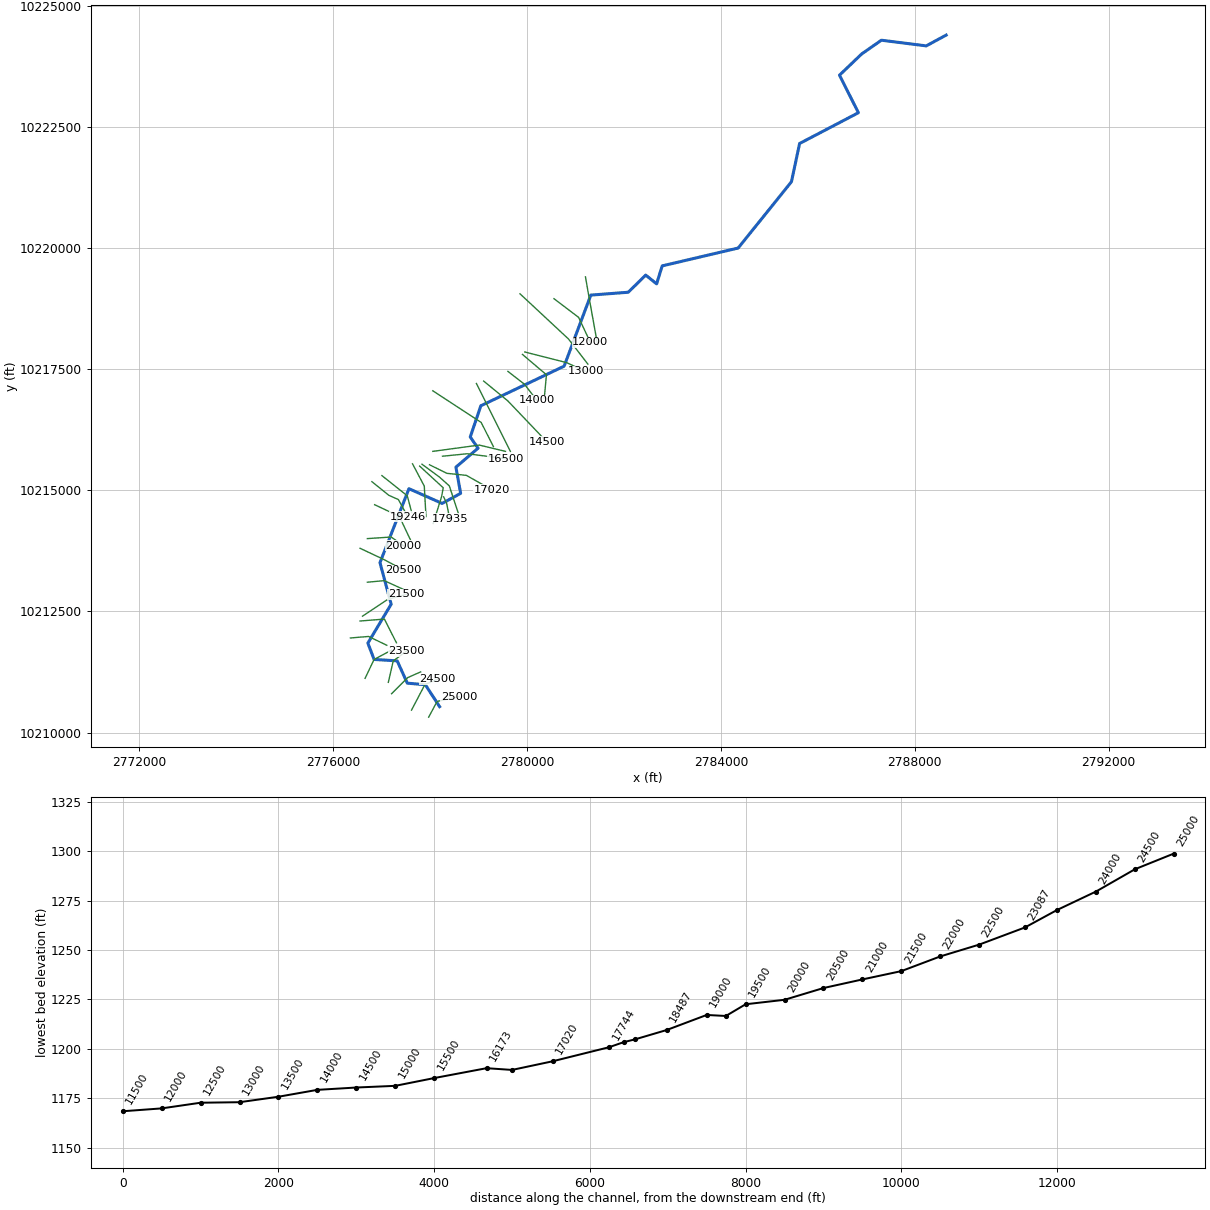
--- SANFERNANDO010.prj (project) ---

Proj Title=SANFERNANDO010 Base Level Engineering
Current Plan=p01
Default Exp/Contr=0.3,0.1
English Units
Geom File=g01
Flow File=f01
Plan File=p01
Y Axis Title=Elevation
X Axis Title(PF)=Main Channel Distance
X Axis Title(XS)=Station
BEGIN DESCRIPTION:
SANFERNANDO010
END DESCRIPTION:
DSS Export Rating Curves= 0
DSS Export Rating Curve Sorted= 0
DSS Export Volume Flow Curves= 0
DXF OffsetX= 0
DXF OffsetY= 0
DXF ScaleX= 1
DXF ScaleY= 10

--- SANFERNANDO010.p01 (plan) ---

Plan Title=Multiple Run
Short Identifier=Multiple
Geom File=g01
Flow File=f01
Subcritical Flow
K Sum by GR= 0
Std Step Tol= 0.01
Critical Tol= 0.01
Num of Std Step Trials= 20
Max Error Tol= 0.3
Flow Tol Ratio= 0.001
Split Flow NTrial= 30
Split Flow Tol= 0.02
Split Flow Ratio= 0.02
Log Output Level= 0
Friction Slope Method= 1
Unsteady Friction Slope Method= 2
Unsteady Bridges Friction Slope Method= 1
Parabolic Critical Depth
Global Vel Dist=  1 , 1 , 1
Global Log Level= 0
CheckData=True
Encroach Param= -1, 0, 0, 0
BEGIN DESCRIPTION:
Multiple Run
END DESCRIPTION:

--- SANFERNANDO010.f01 (steady flow) ---

Flow Title=Multiple
Number of Profiles=7
Profile Names=10-year,25-year,50-year,1pct_min,100-year,1pct_plu,500-year
River Rch & RM= SANFERNANDO010,Reach-1,25000
     412     661     999     778    1343    2319    1859
River Rch & RM= SANFERNANDO010,Reach-1,17020
     762    1280    1738    1021    2358    5444    3226
River Rch & RM= SANFERNANDO010,Reach-1,9413
     834    1412    1892    1100    2571    6014    3515
River Rch & RM= SANFERNANDO010,Reach-1,7500
    1008    1723    2406    1401    3296    7755    4496
River Rch & RM= SANFERNANDO010,Reach-1,6000
    1280    2226    3104    2535    4286    7248    5843
River Rch & RM= SANFERNANDO010,Reach-1,1000
    1326    2312    3204    2280    4430    8606    6039
Boundary for River Rch & Prof#=SANFERNANDO010,Reach-1,1
Up Type=0
Dn Type=3
Dn Slope=0.005
Boundary for River Rch & Prof#=SANFERNANDO010,Reach-1,2
Up Type=0
Dn Type=3
Dn Slope=0.005
Boundary for River Rch & Prof#=SANFERNANDO010,Reach-1,3
Up Type=0
Dn Type=3
Dn Slope=0.005
Boundary for River Rch & Prof#=SANFERNANDO010,Reach-1,4
Up Type=0
Dn Type=3
Dn Slope=0.005
Boundary for River Rch & Prof#=SANFERNANDO010,Reach-1,5
Up Type=0
Dn Type=3
Dn Slope=0.005
Boundary for River Rch & Prof#=SANFERNANDO010,Reach-1,6
Up Type=0
Dn Type=3
Dn Slope=0.005
Boundary for River Rch & Prof#=SANFERNANDO010,Reach-1,7
Up Type=0
Dn Type=3
Dn Slope=0.005

--- SANFERNANDO010.g01 (geometry) ---

Geom Title=Existing Conditions
Program Version=4.10

River Reach=SANFERNANDO010  ,Reach-1
Reach XY= 30
      2778196.25       10210536.        2777902.       10210988.
       2777529.5       10211021.      2777321.25       10211481.
       2776844.5       10211510.        2776716.       10211847.
        2777197.       10212649.        2776966.       10213507.
       2777563.5       10215033.        2778249.       10214729.
        2778630.       10214937.        2778533.       10215477.
      2778989.75       10215869.       2778828.5       10216099.
      2779046.75       10216744.      2780765.25       10217561.
       2781315.5       10219027.      2782088.25       10219086.
      2782448.75       10219440.      2782673.75       10219259.
       2782788.5       10219630.       2784355.5       10219998.
        2785455.       10221365.      2785623.75       10222155.
      2786836.75       10222790.      2786446.75       10223565.
        2786905.       10224003.      2787311.25       10224286.
      2788236.25       10224169.      2788647.75       10224392.

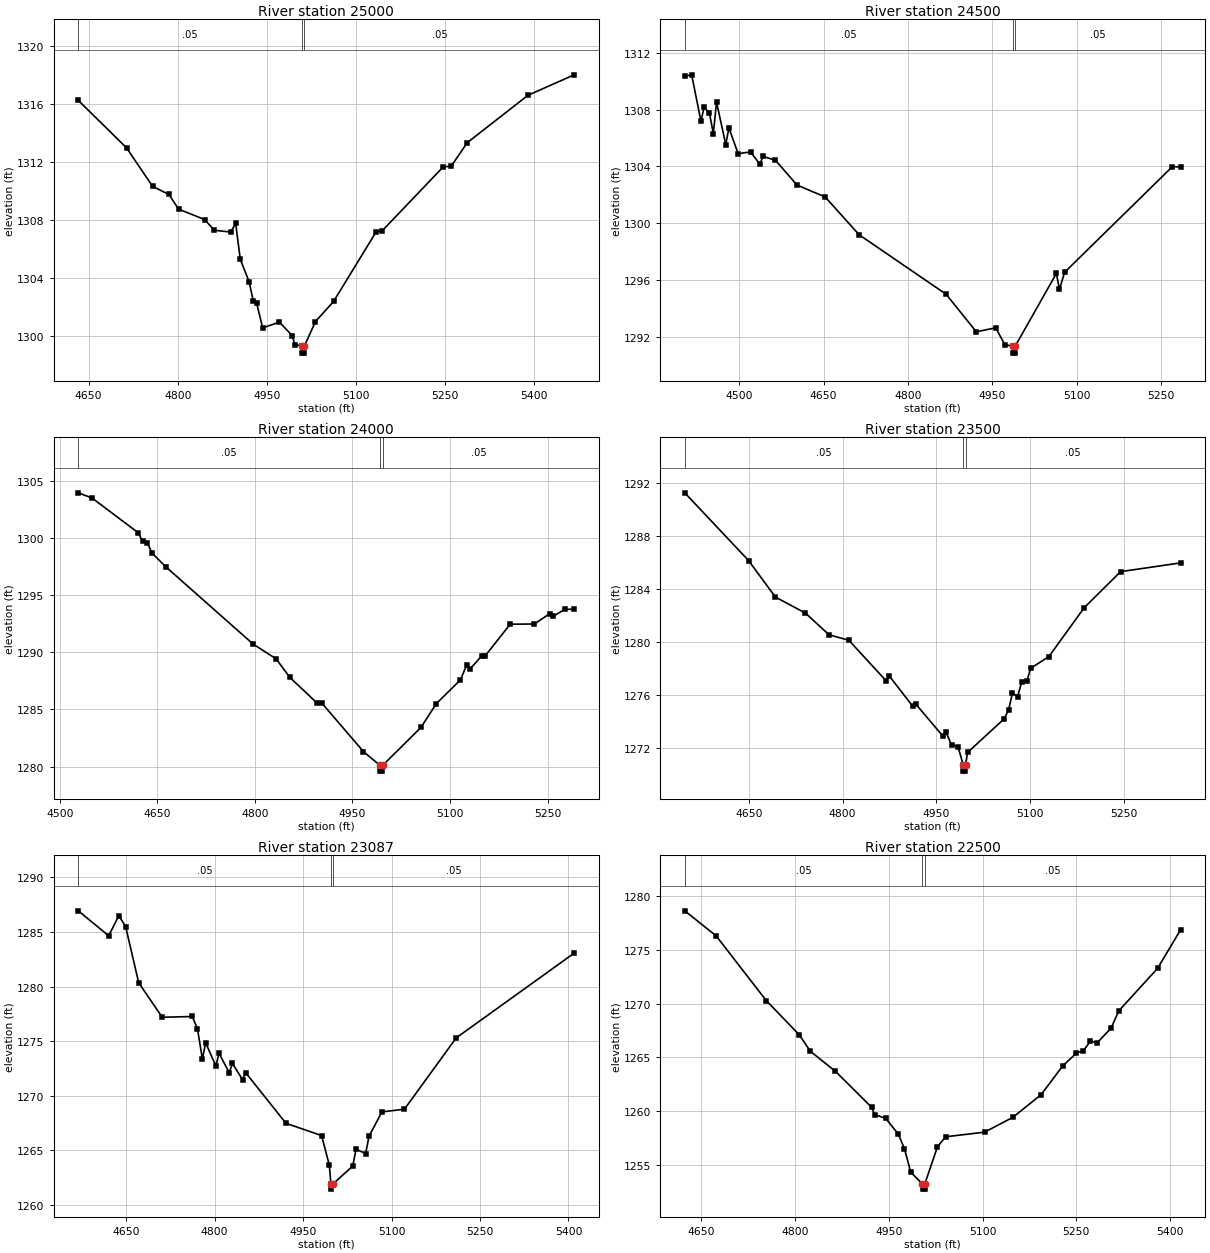
Type RM Length L Ch R = 1 ,25000   ,500,500,500
BEGIN DESCRIPTION:
SANFERNANDO010 49.0
END DESCRIPTION:
XS GIS Cut Line= 3
       2777970.6     10210319.64      2778144.44     10210643.31
      2778601.61       10210742.
#Sta/Elev= 30
  4632.6 1316.25  4713.8 1312.98  4757.7 1310.32  4785.2 1309.76  4801.5 1308.75
  4845.3 1308.03  4861.6 1307.29  4889.2 1307.17  4897.6 1307.76  4905.4 1305.28
  4920.3 1303.73  4927.3  1302.4    4933 1302.26    4943 1300.55  4971.2 1300.95
  4993.1 1300.01  4997.1  1299.4  5009.5 1299.31  5009.7 1298.81  5013.2 1298.81
  5013.5 1299.31    5032 1300.99  5062.6 1302.38  5134.3 1307.19  5144.5 1307.26
  5246.8 1311.65  5260.9 1311.73  5287.7 1313.34    5390 1316.61  5467.7 1318.02
#Mann= 3 ,-1 , 0
  4632.6     .05       0  5009.5     .03       0  5013.5     .05       0
Bank Sta=5009.5,5013.5
XS Rating Curve= 0 ,0
Exp/Cntr=0.3,0.1

Type RM Length L Ch R = 1 ,24500   ,500,500,500
BEGIN DESCRIPTION:
SANFERNANDO010 48.0
END DESCRIPTION:
XS GIS Cut Line= 3
      2777616.57     10210464.29      2777893.48     10210992.74
      2778155.69     10211103.11
#Sta/Elev= 30
  4403.4 1310.35  4415.6 1310.44  4432.1 1307.18  4437.7 1308.16  4447.2 1307.75
  4454.1 1306.31  4459.8 1308.52  4476.2 1305.54  4481.8 1306.71  4498.2  1304.9
  4520.3 1305.02  4536.7 1304.16  4542.4  1304.7  4564.4 1304.44  4602.9 1302.69
  4652.7 1301.86  4713.2  1299.2  4867.7 1295.02  4921.4 1292.38  4955.9 1292.66
  4972.3 1291.46  4986.7 1291.38    4987 1290.88  4990.5 1290.88  4990.7 1291.38
  5063.7 1296.48  5069.2 1295.36  5078.3 1296.56  5269.9 1303.99  5284.5 1303.96
#Mann= 3 ,-1 , 0
  4403.4     .05       0  4986.7     .05       0  4990.7     .05       0
Bank Sta=4986.7,4990.7
XS Rating Curve= 0 ,0
Exp/Cntr=0.3,0.1

Type RM Length L Ch R = 1 ,24000   ,500,500,500
BEGIN DESCRIPTION:
SANFERNANDO010 47.0
END DESCRIPTION:
XS GIS Cut Line= 3
      2777205.69     10210803.12      2777539.43     10211136.04
      2777805.73     10211253.13
#Sta/Elev= 30
  4528.6 1303.98  4549.8 1303.52  4620.5 1300.49  4627.6 1299.72  4634.7 1299.61
  4641.7 1298.71  4662.9 1297.51  4797.3 1290.73  4832.6 1289.44  4853.8 1287.81
  4896.3 1285.53  4903.4 1285.53    4967 1281.31  4992.4  1280.1  4992.6  1279.6
  4996.1  1279.6  4996.4  1280.1  5055.4 1283.43  5078.8  1285.5  5116.1  1287.6
  5125.4 1288.86  5130.9 1288.55  5148.8  1289.7  5154.3 1289.71  5192.5 1292.47
  5229.8 1292.49  5253.1 1293.39  5258.6 1293.16  5276.4 1293.77  5290.9 1293.79
#Mann= 3 ,-1 , 0
  4528.6     .05       0  4992.4     .05       0  4996.4     .05       0
Bank Sta=4992.4,4996.4
XS Rating Curve= 0 ,0
Exp/Cntr=0.3,0.1

Type RM Length L Ch R = 1 ,23500   ,413,413,413
BEGIN DESCRIPTION:
SANFERNANDO010 46.0
END DESCRIPTION:
XS GIS Cut Line= 3
      2777138.13     10211037.42      2777239.32     10211478.26
      2777511.89     10211682.33
#Sta/Elev= 30
  4547.7 1291.27  4649.8 1286.15  4692.6  1283.4  4740.6 1282.19  4778.4 1280.55
    4810 1280.14  4869.2  1277.1  4874.4 1277.46  4912.1 1275.16  4917.2 1275.31
  4960.1 1272.92  4965.2 1273.22  4974.2 1272.23  4984.5 1272.11  4992.7 1270.76
    4993 1270.26  4996.5 1270.26  4996.7 1270.76  4999.9 1271.67  5057.9 1274.19
  5065.3 1274.85  5071.6 1276.16  5079.9 1275.89  5086.2 1276.96  5094.5 1277.05
  5100.8 1278.03  5129.9 1278.91  5186.2 1282.59  5244.5 1285.32  5340.5 1285.98
#Mann= 3 ,-1 , 0
  4547.7     .05       0  4992.7     .05       0  4996.7     .05       0
Bank Sta=4992.7,4996.7
XS Rating Curve= 0 ,0
Exp/Cntr=0.3,0.1

Type RM Length L Ch R = 1 ,23087   ,587,587,587
BEGIN DESCRIPTION:
SANFERNANDO010 45.0
END DESCRIPTION:
XS GIS Cut Line= 3
      2776658.96     10211120.76       2776844.5       10211510.
      2777205.71     10211703.13
#Sta/Elev= 30
  4568.8 1286.94  4620.3 1284.65  4637.4 1286.49    4649  1285.5  4671.2 1280.34
  4711.1 1277.18    4762 1277.25  4770.8 1276.13  4779.2 1273.34  4784.7 1274.85
  4801.9 1272.71  4807.4 1273.88  4824.6  1272.1  4830.1 1272.94  4847.3 1271.46
  4852.8 1272.08  4920.9 1267.46  4981.3 1266.33  4994.5  1263.6    4997 1261.92
  4997.2 1261.42    5001 1261.92  5034.1 1263.53  5039.7 1265.08    5056 1264.68
  5061.7 1266.26  5083.6  1268.5  5121.8 1268.75  5209.6 1275.29  5409.6 1283.06
#Mann= 3 ,-1 , 0
  4568.8     .05       0    4997     .05       0    5001     .05       0
Bank Sta=4997,5001
XS Rating Curve= 0 ,0
Exp/Cntr=0.3,0.1

Type RM Length L Ch R = 1 ,22500   ,500,500,500
BEGIN DESCRIPTION:
SANFERNANDO010 44.0
END DESCRIPTION:
XS GIS Cut Line= 3
      2776355.73     10211953.12      2776730.43     10211984.35
      2777105.66     10211803.12
#Sta/Elev= 30
    4624 1278.64  4674.1 1276.31  4754.4 1270.28  4807.1  1267.1  4824.6 1265.58
  4864.8 1263.71  4922.5 1260.37  4927.5 1259.69  4945.1 1259.33  4965.1 1257.89
  4975.2 1256.51  4985.2 1254.32  5003.8 1253.25  5004.1 1252.75  5007.6 1252.75
  5007.8 1253.25    5028  1256.7    5041 1257.62  5103.3 1258.05  5148.5 1259.43
  5193.7 1261.54  5227.9 1264.19  5250.1  1265.4  5261.3 1265.64  5272.6 1266.51
  5283.5 1266.37  5305.7 1267.74  5317.8 1269.33    5380  1273.3  5416.7 1276.88
#Mann= 3 ,-1 , 0
    4624     .05       0  5003.8     .05       0  5007.8     .05       0
Bank Sta=5003.8,5007.8
XS Rating Curve= 0 ,0
Exp/Cntr=0.3,0.1

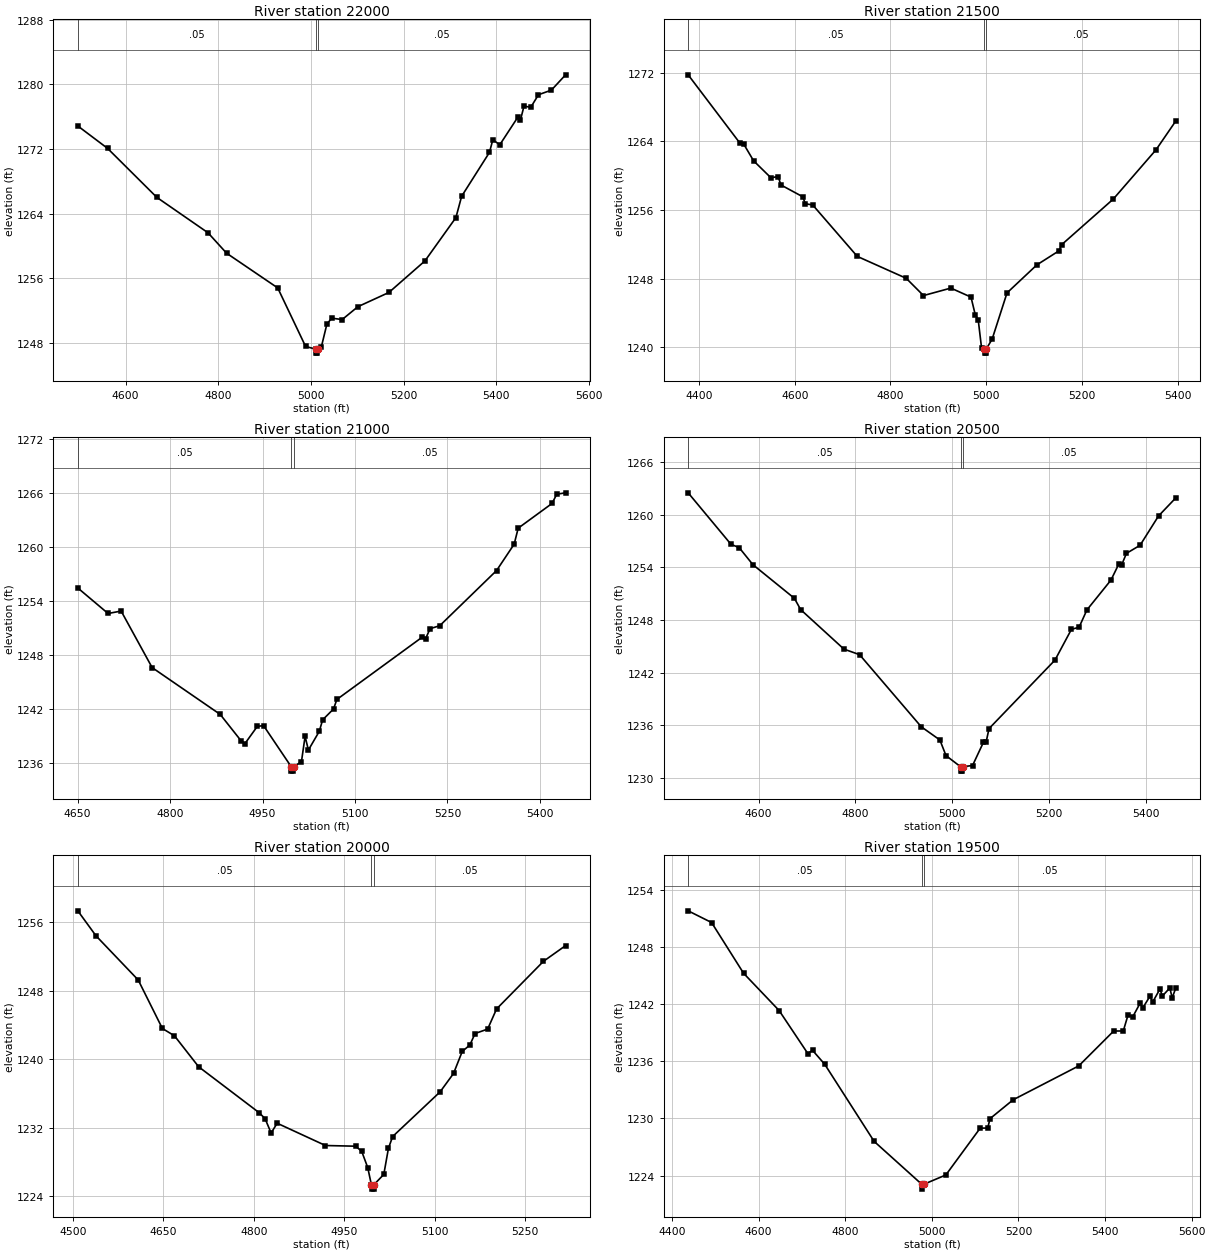
Type RM Length L Ch R = 1 ,22000   ,500,500,500
BEGIN DESCRIPTION:
SANFERNANDO010 43.0
END DESCRIPTION:
XS GIS Cut Line= 3
      2776555.63     10212303.11      2777057.35     10212343.04
       2777305.7     10211853.08
#Sta/Elev= 30
  4496.7 1274.85  4560.9 1272.08  4667.3 1266.02  4777.6 1261.65  4817.8 1259.12
  4928.1 1254.83  4988.3 1247.59  5010.1 1247.27  5010.3 1246.77  5013.8 1246.77
  5014.1 1247.27  5022.3 1247.55  5034.3 1250.38  5044.8 1251.09  5067.2 1250.92
  5101.1 1252.51  5168.1 1254.27  5245.8 1258.17  5312.6 1263.52    5325 1266.16
    5385 1271.58  5392.3 1273.15  5407.3 1272.52  5446.2 1275.93  5451.9 1275.58
  5459.6 1277.31  5474.1 1277.15  5490.8 1278.71  5518.7 1279.28  5549.3 1281.17
#Mann= 3 ,-1 , 0
  4496.7     .05       0  5010.1     .05       0  5014.1     .05       0
Bank Sta=5010.1,5014.1
XS Rating Curve= 0 ,0
Exp/Cntr=0.3,0.1

Type RM Length L Ch R = 1 ,21500   ,500,500,500
BEGIN DESCRIPTION:
SANFERNANDO010 42.0
END DESCRIPTION:
XS GIS Cut Line= 3
       2776605.7     10212403.12      2777123.89     10212748.07
       2777505.7     10212853.12
#Sta/Elev= 30
  4377.5 1271.73  4485.6 1263.78  4493.2  1263.7  4514.2 1261.72  4550.3 1259.75
  4565.3 1259.89  4571.3 1258.91  4616.4 1257.55  4622.4 1256.72  4637.5 1256.59
  4730.6  1250.6  4832.8 1248.05  4868.9 1246.04    4926 1246.91  4968.1 1245.86
  4977.1 1243.78  4983.1 1243.24  4990.1 1239.96  4996.1 1239.84  4996.3 1239.34
  4999.8 1239.34  5000.1 1239.84  5012.2 1240.96  5043.3 1246.35  5105.6 1249.61
  5151.6 1251.24  5157.4 1251.96  5265.2 1257.27  5354.5 1263.01    5396 1266.38
#Mann= 3 ,-1 , 0
  4377.5     .05       0  4996.1     .05       0  5000.1     .05       0
Bank Sta=4996.1,5000.1
XS Rating Curve= 0 ,0
Exp/Cntr=0.3,0.1

Type RM Length L Ch R = 1 ,21000   ,500,500,500
BEGIN DESCRIPTION:
SANFERNANDO010 41.0
END DESCRIPTION:
XS GIS Cut Line= 3
      2776705.67     10213103.11      2777053.81     10213136.13
      2777455.69     10212953.11
#Sta/Elev= 30
  4650.3 1255.44  4699.4 1252.61  4720.6 1252.88  4770.9 1246.61  4881.3 1241.42
  4915.8 1238.44  4921.5 1238.19  4941.6  1240.1  4951.7 1240.17  4996.4 1235.63
  4996.7 1235.13  5000.2 1235.13  5000.4 1235.63  5013.1 1236.17    5019 1238.98
  5024.4 1237.47    5042 1239.54  5047.5 1240.82  5065.1 1242.02  5070.6 1243.08
  5208.9 1249.98  5214.4  1249.8  5221.8 1250.93  5237.4 1251.25  5329.6 1257.37
  5358.2  1260.3  5364.7 1262.07  5419.6 1264.81  5427.3 1265.84  5441.6 1265.99
#Mann= 3 ,-1 , 0
  4650.3     .05       0  4996.4     .05       0  5000.4     .05       0
Bank Sta=4996.4,5000.4
XS Rating Curve= 0 ,0
Exp/Cntr=0.3,0.1

Type RM Length L Ch R = 1 ,20500   ,500,500,500
BEGIN DESCRIPTION:
SANFERNANDO010 40.0
END DESCRIPTION:
XS GIS Cut Line= 3
      2776555.69     10213803.11      2777049.03      10213570.8
      2777455.73     10213353.09
#Sta/Elev= 30
  4454.7 1262.51  4543.1 1256.64    4560 1256.26  4588.3 1254.32    4674 1250.48
  4686.8  1249.2  4776.2 1244.69  4808.4 1244.06  4935.7 1235.84  4974.2 1234.33
  4986.8 1232.55  5016.9 1231.28  5017.1 1230.78  5020.6 1230.78  5020.9 1231.28
  5041.6 1231.42  5063.9 1234.05  5069.6  1234.1  5075.6 1235.63  5211.7 1243.44
  5245.7 1246.95  5261.4 1247.18  5277.6 1249.16  5327.2 1252.56  5343.4 1254.39
  5349.1 1254.27  5359.2 1255.61  5387.3 1256.53  5425.5 1259.88  5461.3 1261.95
#Mann= 3 ,-1 , 0
  4454.7     .05       0  5016.9     .05       0  5020.9     .05       0
Bank Sta=5016.9,5020.9
XS Rating Curve= 0 ,0
Exp/Cntr=0.3,0.1

Type RM Length L Ch R = 1 ,20000   ,500,500,500
BEGIN DESCRIPTION:
SANFERNANDO010 39.0
END DESCRIPTION:
XS GIS Cut Line= 3
      2776705.67     10214003.11      2777196.56     10214036.21
       2777455.7      10213853.1
#Sta/Elev= 30
    4508 1257.31  4538.1  1254.4  4608.2 1249.24  4648.3 1243.58  4668.4 1242.72
  4708.5 1239.11  4808.7 1233.76  4818.7 1233.06  4828.7 1231.38  4838.8 1232.52
  4918.9 1229.92  4969.1 1229.84  4979.1 1229.23  4989.1 1227.33  4995.1 1225.33
  4995.3 1224.83  4998.8 1224.83  4999.1 1225.33  5015.7 1226.55  5023.4  1229.6
  5030.4 1230.97  5109.1 1236.18  5131.4 1238.33  5145.9 1240.91  5158.4 1241.64
  5167.1 1242.99    5188 1243.51  5202.8 1245.86  5280.6 1251.42  5317.3 1253.25
#Mann= 3 ,-1 , 0
    4508     .05       0  4995.1     .03       0  4999.1     .05       0
Bank Sta=4995.1,4999.1
XS Rating Curve= 0 ,0
Exp/Cntr=0.3,0.1

Type RM Length L Ch R = 1 ,19500   ,254,254,254
BEGIN DESCRIPTION:
SANFERNANDO010 38.0
END DESCRIPTION:
XS GIS Cut Line= 3
      2776855.72     10214703.09      2777364.74     10214462.78
      2777605.66     10213953.15
#Sta/Elev= 30
  4437.1 1251.82  4491.2 1250.59  4565.1 1245.26  4647.2 1241.34  4713.5 1236.82
  4724.4 1237.16  4752.7 1235.68  4866.6 1227.59  4976.9 1223.07  4977.2 1222.57
  4980.9 1223.07  5032.3 1224.06  5111.6 1228.98  5128.9 1228.99  5134.4 1229.98
  5187.7 1231.96  5339.2 1235.52    5420 1239.19  5442.1 1239.19    5453 1240.86
  5464.2  1240.7  5481.3 1242.14  5486.9  1241.6  5504.1 1242.87  5509.6  1242.2
  5526.8  1243.6  5532.4 1242.87  5549.6 1243.71  5555.1 1242.67  5563.7 1243.76
#Mann= 3 ,-1 , 0
  4437.1     .05       0  4976.9     .03       0  4980.9     .05       0
Bank Sta=4976.9,4980.9
XS Rating Curve= 0 ,0
Exp/Cntr=0.3,0.1

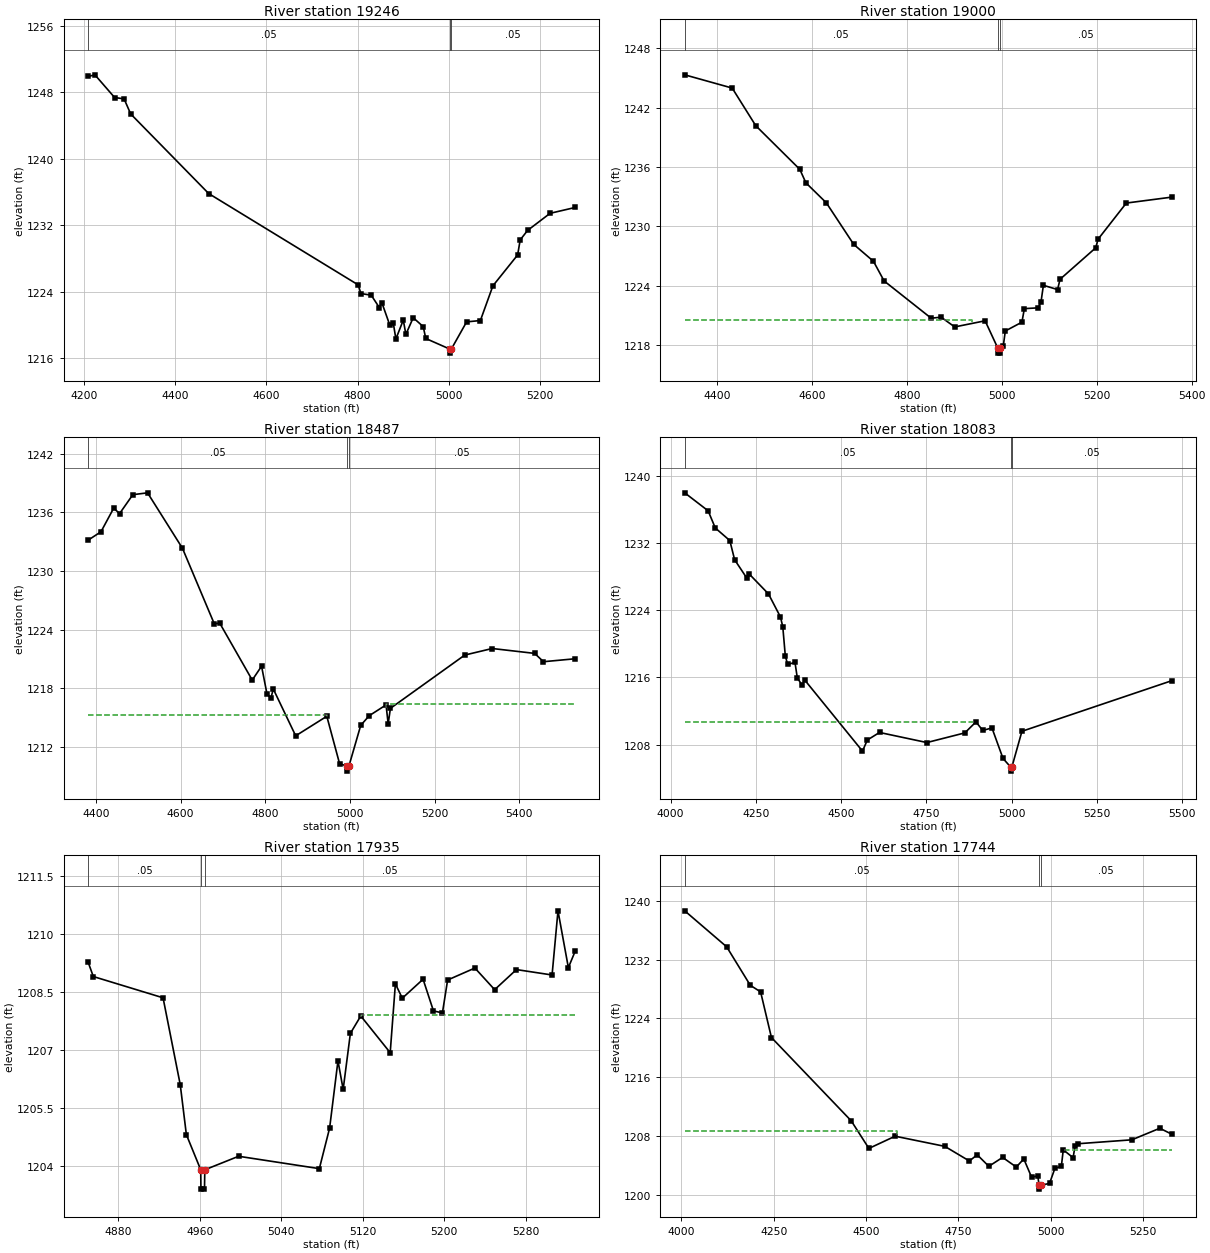
Type RM Length L Ch R = 1 ,19246   ,246,246,246
BEGIN DESCRIPTION:
Mapping XS f40f1f9f
END DESCRIPTION:
XS GIS Cut Line= 4
      2776799.56     10215178.08      2777148.55      10214896.8
      2777346.46     10214808.26      2777539.15     10214454.13
#Sta/Elev= 30
  4208.6 1249.92  4223.7 1250.12  4266.9 1247.39  4287.7 1247.23  4302.1 1245.42
  4473.2 1235.84  4801.1 1224.85  4807.1 1223.81  4829.7 1223.61  4847.5 1222.12
  4852.9 1222.73  4870.5    1220  4878.1 1220.25  4883.8 1218.34    4900 1220.62
  4905.7  1218.9  4921.8  1220.9  4943.7 1219.83  4949.4  1218.4  5001.5 1217.14
  5001.8 1216.64  5005.5 1217.14  5038.9  1220.4  5069.1 1220.56  5096.6 1224.74
  5150.8 1228.45  5156.4 1230.26  5172.6  1231.4    5222 1233.46  5276.8 1234.16
#Mann= 3 ,-1 , 0
  4208.6     .05       0  5001.5     .05       0  5005.5     .05       0
Bank Sta=5001.5,5005.5
XS Rating Curve= 0 ,0
Exp/Cntr=0.3,0.1

Type RM Length L Ch R = 1 ,19000   ,513,513,513
BEGIN DESCRIPTION:
SANFERNANDO010 37.0
END DESCRIPTION:
XS GIS Cut Line= 3
      2777005.71     10215303.09      2777529.35     10214886.57
       2777621.2     10214540.45
#Sta/Elev= 30
  4330.9 1245.31    4431 1243.97  4480.6 1240.17  4573.6 1235.75  4586.4 1234.39
  4629.6 1232.36  4687.3 1228.16  4728.9 1226.45  4751.4 1224.46  4850.7 1220.69
  4871.5  1220.8  4900.3 1219.81  4964.4 1220.43  4991.2 1217.66  4991.5 1217.16
    4995 1217.16  4995.2 1217.66  5002.6 1217.84    5007  1219.4    5042 1220.29
  5047.2 1221.66    5076 1221.74  5082.2 1222.31  5087.3 1224.02  5117.2 1223.59
  5122.4 1224.63  5197.6 1227.81  5202.7 1228.69  5262.2 1232.34  5358.1 1232.94
#Mann= 3 ,-1 , 0
  4330.9     .05       0  4991.2     .03       0  4995.2     .05       0
#XS Ineff= 2 , 0
         4937.05 1220.56
Permanent Ineff=
       F       F
Bank Sta=4991.2,4995.2
XS Rating Curve= 0 ,0
Exp/Cntr=0.3,0.1

Type RM Length L Ch R = 1 ,18487   ,404,404,404
BEGIN DESCRIPTION:
Mapping XS 581461f0
END DESCRIPTION:
XS GIS Cut Line= 3
      2777637.24     10215546.69      2777880.32     10215086.58
      2777915.02     10214457.71
#Sta/Elev= 30
  4381.5 1233.16  4412.1 1234.03  4442.1 1236.44  4456.1 1235.89  4487.3 1237.82
  4522.1 1238.01  4604.5 1232.34  4679.6 1224.62  4692.6 1224.68  4769.3 1218.86
  4791.3 1220.28    4804 1217.48  4813.3    1217    4819 1217.95  4871.9 1213.16
  4945.4 1215.16  4975.5 1210.32  4993.5 1210.05  4993.7 1209.55  4997.5 1210.05
  5025.5 1214.23  5045.6 1215.22  5085.3 1216.32  5090.3 1214.39  5095.6 1215.97
  5271.2 1221.42    5336 1222.09  5436.2 1221.59  5457.1 1220.74  5531.7 1221.04
#Mann= 3 ,-1 , 0
  4381.5     .05       0  4993.5     .03       0  4997.5     .05       0
#XS Ineff= 2 , 0
         4946.14 1215.24 5086.14         1216.46
Permanent Ineff=
       F       F
Bank Sta=4993.5,4997.5
XS Rating Curve= 0 ,0
Exp/Cntr=0.3,0.1

Type RM Length L Ch R = 1 ,18083   ,148,148,148
BEGIN DESCRIPTION:
Mapping XS 65198fd3
END DESCRIPTION:
XS GIS Cut Line= 4
      2777784.85     10215498.89      2778270.94     10215051.86
      2778236.22     10214865.23      2778062.62     10214314.05
#Sta/Elev= 30
  4041.2 1237.96  4109.8 1235.82  4130.8 1233.78  4173.4 1232.28  4187.5    1230
  4222.7 1227.85  4230.1 1228.31  4286.8 1225.93  4321.9 1223.19  4328.7 1222.03
  4336.1 1218.56  4342.9 1217.55  4364.5 1217.78  4371.3 1215.94  4385.5 1215.07
  4392.8  1215.7  4562.4 1207.23  4576.6 1208.55  4612.3 1209.45  4751.2 1208.25
  4862.5  1209.4  4895.2 1210.71  4914.9 1209.69    4942 1209.99  4974.4 1206.36
  4996.5 1205.35  4996.7 1204.85  5000.5 1205.35  5029.9 1209.59  5469.3 1215.61
#Mann= 3 ,-1 , 0
  4041.2     .05       0  4996.5     .03       0  5000.5     .05       0
#XS Ineff= 2 , 0
         4891.82 1210.75
Permanent Ineff=
       F       F
Bank Sta=4996.5,5000.5
XS Rating Curve= 0 ,0
Exp/Cntr=0.3,0.1

Type RM Length L Ch R = 1 ,17935   ,191,191,191
BEGIN DESCRIPTION:
Mapping XS 103af480
END DESCRIPTION:
XS GIS Cut Line= 3
      2778279.64     10214865.21      2778340.39     10214735.02
       2778405.2     10214406.62
#Sta/Elev= 30
  4850.2 1209.29  4855.4 1208.91  4923.9 1208.36  4940.8 1206.11  4946.8 1204.82
  4960.9 1203.91  4961.1 1203.41  4964.6 1203.41  4964.9 1203.91  4998.1 1204.26
  5077.4 1203.94  5087.5 1204.99  5095.7 1206.73  5100.8 1205.99  5107.9 1207.44
  5118.1 1207.89    5147 1206.94  5152.1 1208.72  5158.9 1208.35  5179.3 1208.84
  5189.5 1208.02  5198.3 1207.97  5203.4 1208.82  5230.2 1209.13  5249.6 1208.57
    5271 1209.09    5306 1208.95  5311.8 1210.61    5322 1209.14  5328.6 1209.56
#Mann= 3 ,-1 , 0
  4850.2     .05       0  4960.9     .05       0  4964.9     .05       0
#XS Ineff= 2 , 0
                         5118.75         1207.91
Permanent Ineff=
       F       F
Bank Sta=4960.9,4964.9
XS Rating Curve= 0 ,0
Exp/Cntr=0.3,0.1

Type RM Length L Ch R = 1 ,17744   ,724,724,724
BEGIN DESCRIPTION:
Mapping XS a7b57a4a
END DESCRIPTION:
XS GIS Cut Line= 4
      2777832.59     10215537.96      2778192.82     10215273.21
      2778396.81     10215090.92      2778583.46      10214522.3
#Sta/Elev= 30
  4008.9 1238.62  4122.5 1233.73  4186.5  1228.5  4214.4 1227.61  4243.7 1221.41
  4459.8 1210.09  4507.7 1206.34  4578.7    1208  4713.3 1206.62  4779.9 1204.63
  4800.9 1205.48  4832.5 1203.91  4869.8 1205.12  4906.8 1203.81  4927.2 1204.91
  4948.3 1202.43  4965.2 1202.61  4968.5 1201.31  4968.7 1200.81  4972.5 1201.31
    4997  1201.6  5011.4 1203.63  5028.9 1203.91  5034.1 1206.15  5060.7 1205.08
  5065.9 1206.64  5074.6 1206.98  5219.8 1207.51  5295.6 1209.08    5328 1208.27
#Mann= 3 ,-1 , 0
  4008.9     .05       0  4968.5     .05       0  4972.5     .05       0
#XS Ineff= 2 , 0
         4582.51 1208.75 5034.89         1206.15
Permanent Ineff=
       F       F
Bank Sta=4968.5,4972.5
XS Rating Curve= 0 ,0
Exp/Cntr=0.3,0.1

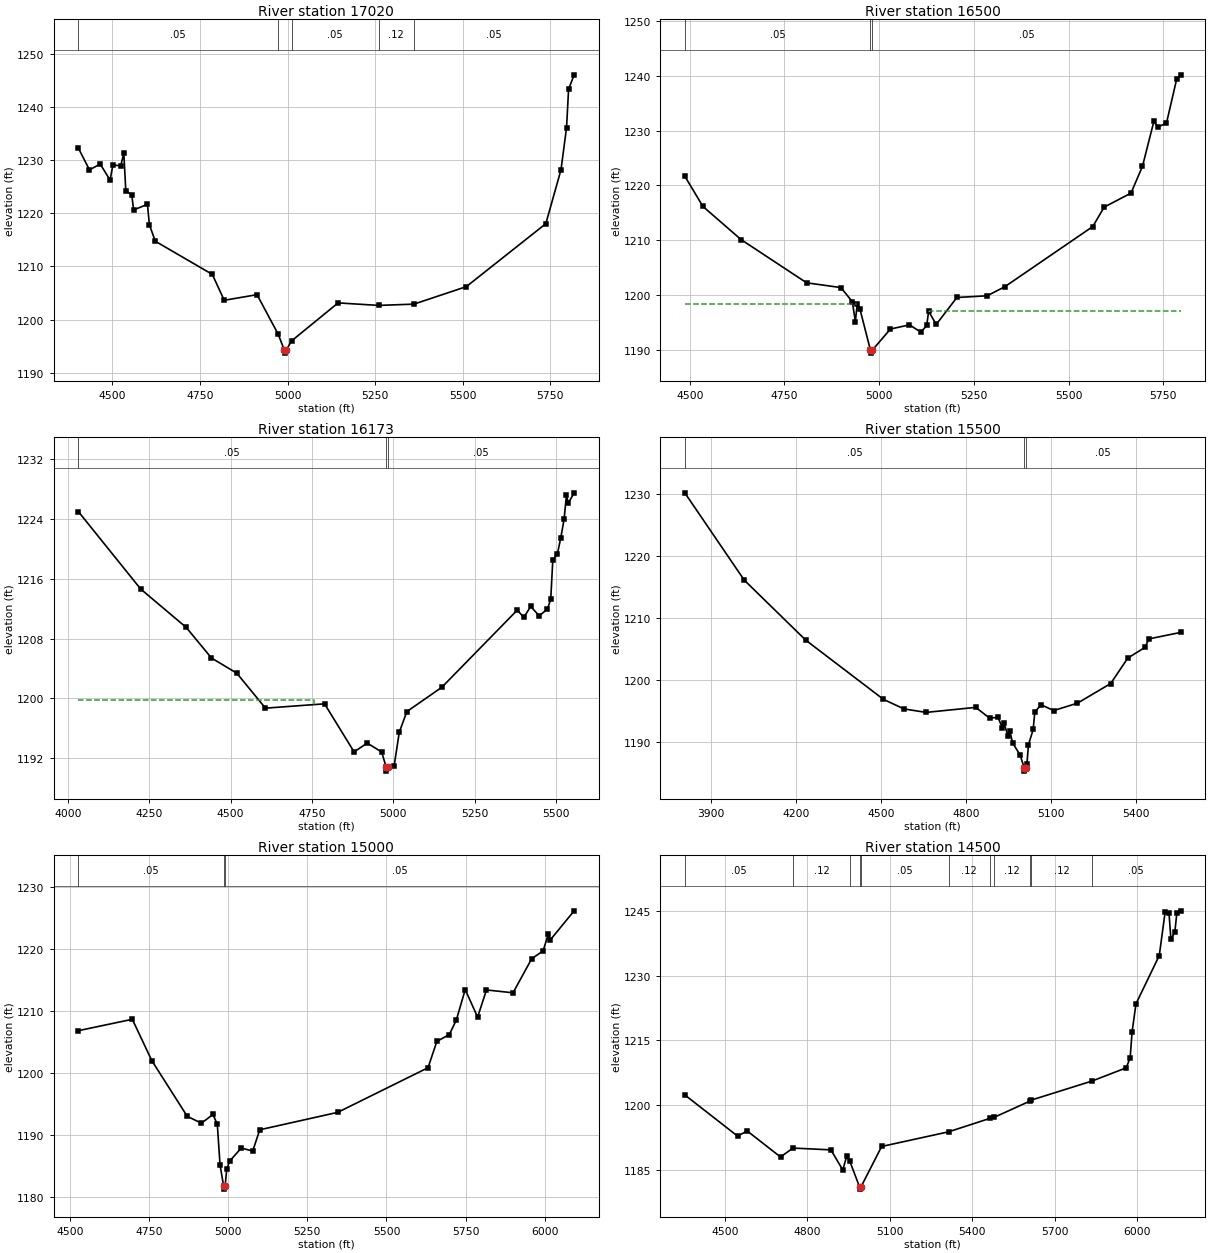
Type RM Length L Ch R = 1 ,17020   ,520,520,520
BEGIN DESCRIPTION:
Mapping XS 70a734fc
END DESCRIPTION:
XS GIS Cut Line= 4
      2777987.12       10215527.      2778346.46     10215349.93
       2778747.5     10215308.26       2779280.6     10215008.08
#Sta/Elev= 30
  4402.6 1232.25  4434.4 1228.16  4465.1 1229.25  4493.2 1226.23  4501.3 1229.08
  4523.6 1228.91  4532.5 1231.28  4538.1 1224.23    4555 1223.48  4560.5 1220.63
  4599.9 1221.67  4605.5 1217.82  4622.4 1214.74  4785.1 1208.51  4819.1 1203.64
  4912.8  1204.7  4973.3 1197.25  4991.2 1194.21  4991.5 1193.71  4995.6 1194.21
  5011.4 1196.01  5144.2 1203.15  5259.6 1202.68  5360.7 1202.92  5510.4 1206.21
  5737.3 1218.04  5780.6 1228.17  5796.5 1236.11  5802.3 1243.34  5818.2 1246.02
#Mann= 5 ,-1 , 0
  4402.6     .05       0  4973.3     .05       0  5011.4     .05       0
  5259.6     .12       0  5360.7     .05       0
Bank Sta=4991.2,4995.6
XS Rating Curve= 0 ,0
Exp/Cntr=0.3,0.1

Type RM Length L Ch R = 1 ,16500   ,327,327,327
BEGIN DESCRIPTION:
SANFERNANDO010 33.0
END DESCRIPTION:
XS GIS Cut Line= 3
      2778255.67     10215703.11      2778766.23     10215754.05
      2779555.71     10215653.11
#Sta/Elev= 30
  4486.9 1221.66  4534.7 1216.14  4635.3 1210.09  4808.5 1202.19    4899 1201.32
  4929.1 1198.75  4937.2 1195.12  4942.2 1198.38  4949.2 1197.43  4977.1 1189.85
  4977.4 1189.35  4981.5 1189.85  5029.7 1193.75  5080.1 1194.51  5110.3 1193.18
  5125.6 1194.41  5130.6 1196.98  5150.7 1194.59  5205.3 1199.51  5285.1 1199.82
  5332.1 1201.49    5564 1212.47    5594 1216.01  5664.8 1218.57  5695.1 1223.44
  5725.3 1231.68  5735.4 1230.64  5758.5 1231.34  5785.8 1239.49  5795.9 1240.17
#Mann= 3 ,-1 , 0
  4486.9     .05       0  4977.1     .05       0  4981.5     .05       0
#XS Ineff= 2 , 0
          4942.5 1198.38 5131.82         1197.06
Permanent Ineff=
       F       F
Bank Sta=4977.1,4981.5
XS Rating Curve= 0 ,0
Exp/Cntr=0.3,0.1

Type RM Length L Ch R = 1 ,16173   ,673,673,673
BEGIN DESCRIPTION:
SANFERNANDO010 32.0
END DESCRIPTION:
XS GIS Cut Line= 3
      2778055.65     10215803.11        2779015.       10215933.
      2779555.72      10215803.1
#Sta/Elev= 30
  4031.9 1225.02  4223.7 1214.63  4363.6 1209.49  4441.2 1205.39  4518.9 1203.36
  4607.1 1198.67  4788.8 1199.25  4879.6 1192.81    4920 1193.99  4964.5 1192.79
  4978.3 1190.73  4978.6 1190.23  4982.8 1190.73  5002.9 1190.98  5018.5 1195.44
  5041.8 1198.21  5149.6 1201.48  5381.2 1211.81  5401.4 1210.83  5422.4  1212.3
  5448.6 1211.05  5473.8 1211.94  5484.1 1213.26  5490.5 1218.56  5504.6 1219.35
  5514.9 1221.49  5525.2 1223.98  5532.5 1227.29  5537.7 1226.13  5556.1 1227.53
#Mann= 3 ,-1 , 0
  4031.9     .05       0  4978.3     .03       0  4982.8     .05       0
#XS Ineff= 2 , 0
         4756.36  1199.7
Permanent Ineff=
       F       F
Bank Sta=4978.3,4982.8
XS Rating Curve= 0 ,0
Exp/Cntr=0.3,0.1

Type RM Length L Ch R = 1 ,15500   ,500,500,500
BEGIN DESCRIPTION:
SANFERNANDO010 31.0
END DESCRIPTION:
XS GIS Cut Line= 3
      2778055.66     10217053.13      2779053.16     10216400.54
       2779305.7     10215903.08
#Sta/Elev= 30
    3808 1230.15  4017.6 1216.07  4234.8 1206.37  4509.2 1196.81  4581.6 1195.27
  4659.9 1194.71  4834.9 1195.52  4883.5 1193.79  4913.3 1193.91  4928.4 1192.26
  4934.3 1192.97  4949.4 1190.84  4955.4 1191.72  4964.6 1189.82  4991.6  1187.8
  5006.1 1185.73  5006.4 1185.23  5010.6 1185.73  5015.3 1186.31  5020.9  1189.5
  5037.5 1191.95  5043.2 1194.77  5065.4 1195.94  5109.9 1195.01  5193.4 1196.19
  5311.1 1199.37  5371.5 1203.48  5432.6 1205.22  5445.7 1206.57  5557.9 1207.62
#Mann= 3 ,-1 , 0
    3808     .05       0  5006.1     .05       0  5010.6     .05       0
Bank Sta=5006.1,5010.6
XS Rating Curve= 0 ,0
Exp/Cntr=0.3,0.1

Type RM Length L Ch R = 1 ,15000   ,500,500,500
BEGIN DESCRIPTION:
SANFERNANDO010 30.0
END DESCRIPTION:
XS GIS Cut Line= 3
      2778955.68     10217203.13      2779167.38     10216780.37
       2779655.7     10215803.08
#Sta/Elev= 30
  4527.2 1206.85  4697.6 1208.69  4759.1 1202.03  4870.9 1193.05  4915.6 1191.93
  4952.2 1193.34  4965.9 1191.77  4974.6  1185.2  4985.9  1181.8  4986.2  1181.3
  4990.6  1181.8  4995.7 1184.53    5005 1185.83  5041.7 1187.93  5077.7 1187.44
    5100 1190.87    5346 1193.68  5631.2 1200.88  5659.1 1205.13  5698.3 1206.22
  5720.6 1208.58  5748.6 1213.48  5787.7 1209.04  5815.7 1213.42  5899.6 1212.96
  5958.3 1218.44  5994.6 1219.73  6011.4 1222.52    6017 1221.48  6092.5 1226.18
#Mann= 3 ,-1 , 0
  4527.2     .05       0  4985.9     .05       0  4990.6     .05       0
Bank Sta=4985.9,4990.6
XS Rating Curve= 0 ,0
Exp/Cntr=0.3,0.1

Type RM Length L Ch R = 1 ,14500   ,500,500,500
BEGIN DESCRIPTION:
SANFERNANDO010 29.0
END DESCRIPTION:
XS GIS Cut Line= 3
      2779105.71     10217253.09      2779605.77     10216842.55
      2780405.66     10216003.14
#Sta/Elev= 30
    4353 1202.34  4545.3 1192.77  4580.4 1193.96  4701.7 1187.92  4747.2 1189.99
  4885.4 1189.57  4928.5 1184.91  4942.8 1188.06  4954.4 1186.89  4989.8 1180.95
  4990.2 1180.45  4994.8 1180.95  5070.2 1190.36  5313.8 1193.76  5463.8 1196.87
  5481.1 1197.16  5611.5 1200.93  5614.5 1201.12  5836.6 1205.56  5961.5 1208.64
  5975.7 1211.01  5982.6 1216.95  5996.8 1223.49  6081.7 1234.72  6103.1 1244.85
  6117.2 1244.56  6124.1 1238.54  6138.3 1240.08  6145.6 1244.55  6159.5 1245.11
#Mann= 11 ,-1 , 0
    4353     .05       0  4747.2     .12       0  4954.4     .05       0
  4989.8     .03       0  4994.8     .05       0  5313.8     .12       0
  5463.8     .05       0  5481.1     .12       0  5611.5     .05       0
  5614.5     .12       0  5836.6     .05       0
Bank Sta=4989.8,4994.8
XS Rating Curve= 0 ,0
Exp/Cntr=0.3,0.1

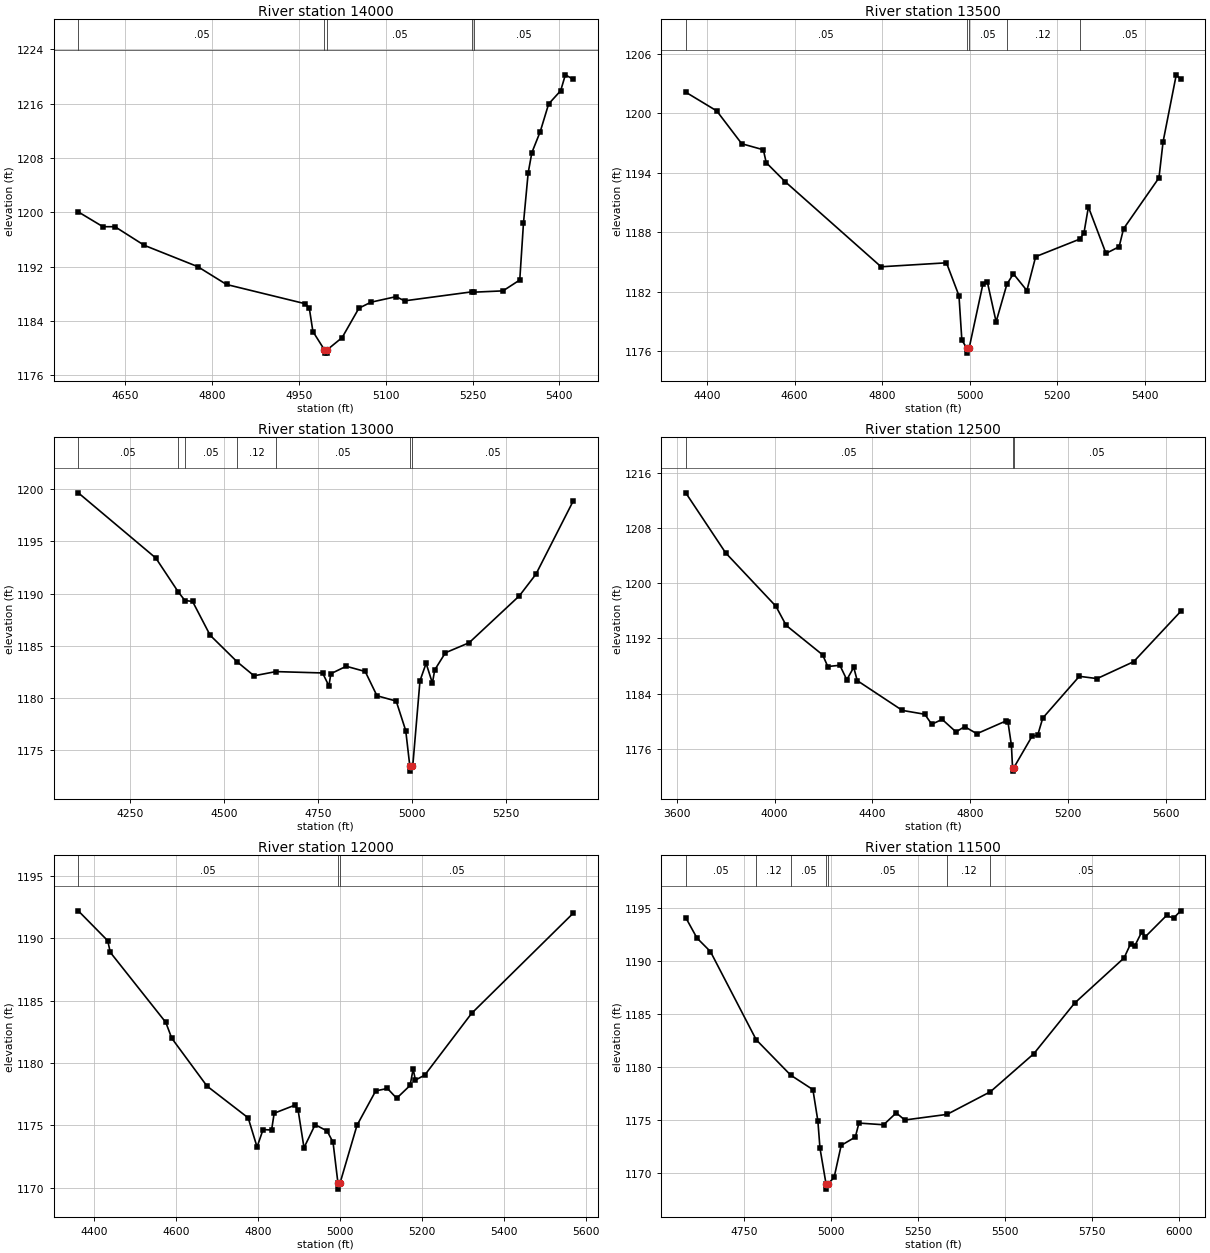
Type RM Length L Ch R = 1 ,14000   ,500,500,500
BEGIN DESCRIPTION:
SANFERNANDO010 28.0
END DESCRIPTION:
XS GIS Cut Line= 3
      2779605.65     10217453.14      2779946.52     10217188.57
      2780205.68     10216853.12
#Sta/Elev= 30
  4568.5 1200.07  4611.1 1197.89  4631.9 1197.89  4682.5 1195.15  4774.9 1192.01
  4824.7 1189.38    4961 1186.54  4967.7 1185.92    4974 1182.45  4993.8 1179.77
  4994.2 1179.27  4998.5 1179.27  4998.8 1179.77  5024.5 1181.56  5053.5 1185.89
  5074.3 1186.77  5117.8 1187.59  5132.3 1186.97    5249  1188.3  5252.9 1188.25
  5302.5 1188.44  5331.5 1190.04  5337.9  1198.4    5346  1205.8  5352.4  1208.8
  5366.9  1211.9  5381.4 1215.97  5402.2 1217.92  5410.3 1220.26  5423.9  1219.6
#Mann= 5 ,-1 , 0
  4568.5     .05       0  4993.8     .05       0  4998.8     .05       0
    5249     .12       0  5252.9     .05       0
Bank Sta=4993.8,4998.8
XS Rating Curve= 0 ,0
Exp/Cntr=0.3,0.1

Type RM Length L Ch R = 1 ,13500   ,500,500,500
BEGIN DESCRIPTION:
SANFERNANDO010 27.0
END DESCRIPTION:
XS GIS Cut Line= 3
      2779905.67     10217803.13      2780400.38     10217383.52
      2780355.68      10216903.1
#Sta/Elev= 30
  4351.3 1202.11  4422.2 1200.22  4479.3 1196.91  4528.7  1196.3  4535.3    1195
  4578.1  1193.1  4797.8  1184.5  4947.2  1184.9  4975.8 1181.58  4982.4 1177.09
  4993.9 1176.29  4994.3 1175.79    4999 1176.29  5030.5 1182.75  5040.6 1182.98
  5060.7 1178.95  5085.4 1182.75  5100.2 1183.79    5131  1182.1  5151.1 1185.52
  5251.9 1187.29  5261.5 1187.92  5271.6 1190.53  5311.8 1185.85  5341.9 1186.52
  5351.9 1188.33  5432.9 1193.47  5442.3 1197.11  5472.4 1203.86  5482.5 1203.41
#Mann= 5 ,-1 , 0
  4351.3     .05       0  4993.9     .05       0    4999     .05       0
  5085.4     .12       0  5251.9     .05       0
Bank Sta=4993.9,4999
XS Rating Curve= 0 ,0
Exp/Cntr=0.3,0.1

Type RM Length L Ch R = 1 ,13000   ,500,500,500
BEGIN DESCRIPTION:
SANFERNANDO010 26.0
END DESCRIPTION:
XS GIS Cut Line= 3
      2779955.64     10217853.12      2780815.89     10217634.06
      2781205.64     10217453.13
#Sta/Elev= 30
  4112.3 1199.64  4318.7  1193.4  4378.4 1190.16  4396.1 1189.34  4416.5 1189.25
  4463.2 1186.02  4535.3 1183.47  4580.1 1182.14  4638.3 1182.54  4762.5 1182.41
  4779.4 1181.17  4784.6 1182.34  4825.5 1183.05    4876 1182.55  4907.3 1180.23
  4958.5 1179.72  4983.9 1176.89  4994.7 1173.52  4995.1 1173.02    5000 1173.52
  5002.6 1173.52  5021.8 1181.66  5038.1 1183.33  5054.9 1181.44    5061  1182.7
  5089.4 1184.34  5152.6  1185.3  5286.4 1189.79  5330.5 1191.86  5429.7 1198.86
#Mann= 7 ,-1 , 0
  4112.3     .05       0  4378.4     .12       0  4396.1     .05       0
  4535.3     .12       0  4638.3     .05       0  4994.7     .03       0
    5000     .05       0
Bank Sta=4994.7,5000
XS Rating Curve= 0 ,0
Exp/Cntr=0.3,0.1

Type RM Length L Ch R = 1 ,12500   ,500,500,500
BEGIN DESCRIPTION:
SANFERNANDO010 25.0
END DESCRIPTION:
XS GIS Cut Line= 3
      2779855.65     10219053.14      2780852.76     10218124.17
       2781255.7     10217603.09
#Sta/Elev= 30
  3637.2 1213.09  3800.2 1204.39  4005.4 1196.66  4047.4 1193.88  4196.4 1189.61
  4217.4 1187.92  4266.8  1188.1  4295.1    1186  4323.4 1187.81  4337.6 1185.88
  4521.8 1181.56  4613.6    1181    4642 1179.55  4684.5 1180.26  4741.2 1178.44
  4776.3 1179.21  4826.2 1178.18  4946.3 1180.05  4953.2  1179.9  4967.4 1176.51
    4972 1173.26  4972.4 1172.76  4977.3 1173.26  5051.9 1177.83  5074.6 1177.95
  5095.4 1180.45  5244.8  1186.5  5317.3 1186.17  5466.7 1188.62  5658.7  1195.9
#Mann= 3 ,-1 , 0
  3637.2     .05       0    4972     .03       0  4977.3     .05       0
Bank Sta=4972,4977.3
XS Rating Curve= 0 ,0
Exp/Cntr=0.3,0.1

Type RM Length L Ch R = 1 ,12000   ,500,500,500
BEGIN DESCRIPTION:
SANFERNANDO010 24.0
END DESCRIPTION:
XS GIS Cut Line= 3
      2780555.67     10218953.12      2781064.15     10218567.77
      2781305.68     10218053.12
#Sta/Elev= 30
    4362 1192.22  4433.8 1189.82    4440 1188.89  4575.3 1183.27  4589.8    1182
  4675.7 1178.16  4776.1 1175.61  4797.8 1173.27  4812.4 1174.67  4833.2 1174.63
  4839.5 1175.98  4889.4 1176.62  4897.7 1176.26  4912.2 1173.21  4939.3 1175.06
  4968.4 1174.56    4983 1173.65  4994.9 1170.39  4995.3 1169.89  5000.2 1170.39
  5041.4 1175.01    5087 1177.77  5115.6 1177.97  5138.1 1177.18  5170.8 1178.21
  5178.3 1179.53  5183.8 1178.64  5206.6 1179.04  5320.7 1183.99  5568.5 1192.03
#Mann= 3 ,-1 , 0
    4362     .05       0  4994.9     .05       0  5000.2     .05       0
Bank Sta=4994.9,5000.2
XS Rating Curve= 0 ,0
Exp/Cntr=0.3,0.1

Type RM Length L Ch R = 1 ,11500   ,500,500,500
BEGIN DESCRIPTION:
SANFERNANDO010 23.0
END DESCRIPTION:
XS GIS Cut Line= 3
      2781205.69     10219403.08      2781277.34     10218991.68
      2781455.68     10218003.13
#Sta/Elev= 30
  4582.4 1194.09  4614.7 1192.16  4653.4 1190.88  4784.9 1182.55  4883.9 1179.21
  4947.8 1177.84  4962.1 1174.88  4968.1 1172.31  4985.5 1168.94    4986 1168.44
  4991.2 1168.94  5008.7 1169.54    5029 1172.57  5069.7 1173.36    5080 1174.68
    5151 1174.52  5187.2 1175.64  5211.9 1174.97  5333.2  1175.5  5457.8 1177.64
  5582.5 1181.23  5699.7 1186.01  5841.9 1190.28  5860.4  1191.6  5872.4  1191.4
  5892.7 1192.74  5902.9 1192.28  5963.9 1194.29  5984.2 1194.04  6004.5 1194.73
#Mann= 7 ,-1 , 0
  4582.4     .05       0  4784.9     .12       0  4883.9     .05       0
  4985.5     .05       0  4991.2     .05       0  5333.2     .12       0
  5457.8     .05       0
Bank Sta=4985.5,4991.2
XS Rating Curve= 0 ,0
Exp/Cntr=0.3,0.1