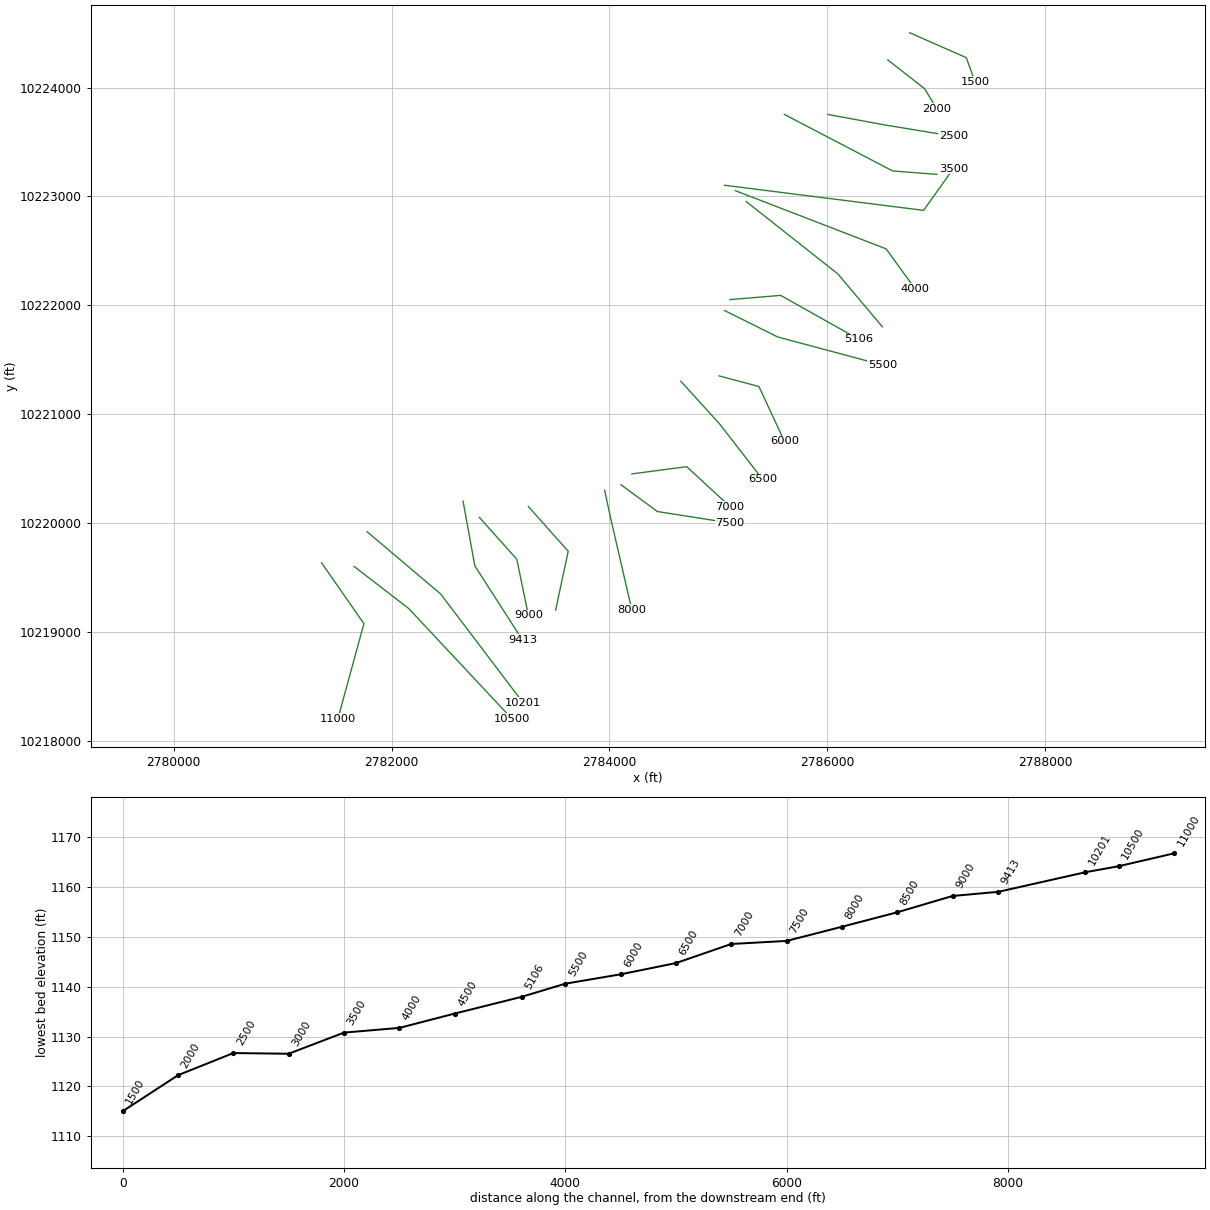
HEC-RAS study SANFERNANDO010.prj: SANFERNANDO010 Base Level Engineering

--- SANFERNANDO010.g01 (geometry) --- (continued)

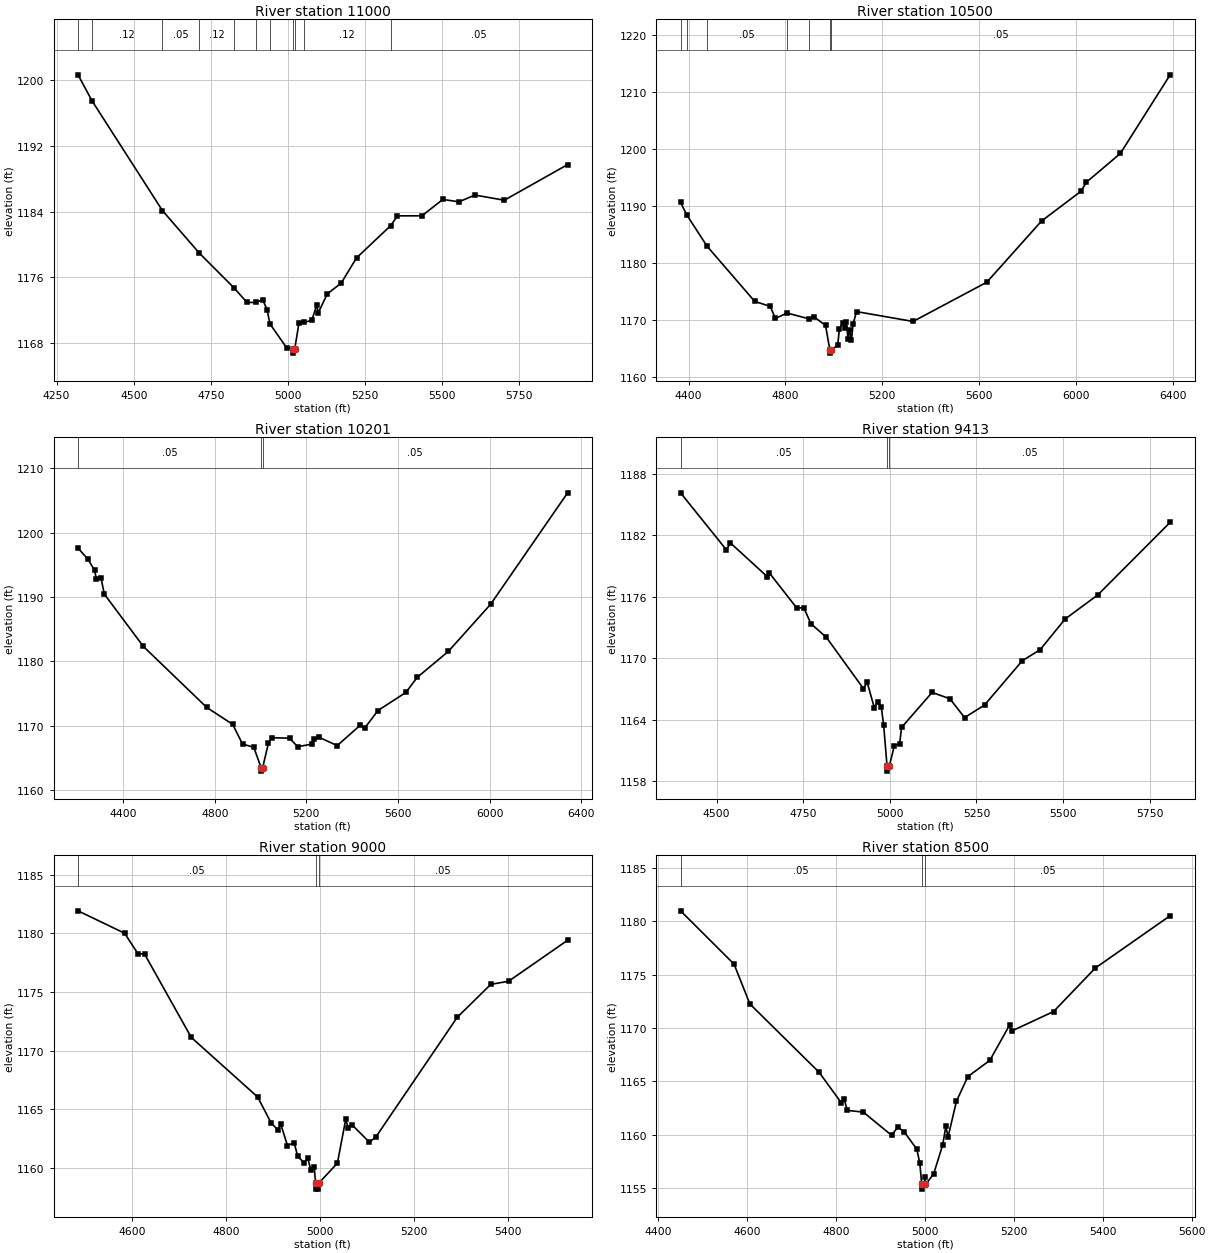
Type RM Length L Ch R = 1 ,11000   ,500,500,500
BEGIN DESCRIPTION:
SANFERNANDO010 22.0
END DESCRIPTION:
XS GIS Cut Line= 3
      2781356.86     10219636.41      2781745.51     10219077.81
      2781505.68     10218203.09
#Sta/Elev= 30
  4319.5 1200.69  4365.2  1197.5  4593.1 1184.12  4712.6 1178.93  4825.5 1174.67
  4867.3  1172.9    4897  1172.9  4917.9 1173.24  4932.6 1172.02  4941.7 1170.29
  4995.6 1167.38  5016.5 1167.21  5016.9 1166.71  5022.2 1167.21    5036 1170.41
  5051.4 1170.47  5077.5  1170.7  5093.4 1172.57  5098.6 1171.65  5127.9 1173.95
  5172.7 1175.25  5222.6 1178.34  5333.4 1182.28  5355.4 1183.47  5434.7 1183.48
  5502.6 1185.48  5554.4 1185.18  5606.3 1186.01  5701.9 1185.38    5907 1189.73
#Mann= 11 ,-1 , 0
  4319.5     .05       0  4365.2     .12       0  4593.1     .05       0
  4712.6     .12       0  4825.5     .05       0    4897     .12       0
  4941.7     .05       0  5016.5     .05       0  5022.2     .05       0
  5051.4     .12       0  5333.4     .05       0
Bank Sta=5016.5,5022.2
XS Rating Curve= 0 ,0
Exp/Cntr=0.3,0.1

Type RM Length L Ch R = 1 ,10500   ,299,299,299
BEGIN DESCRIPTION:
SANFERNANDO010 21.0
END DESCRIPTION:
XS GIS Cut Line= 3
      2781655.71     10219603.09      2782157.07     10219216.51
      2783105.68     10218203.12
#Sta/Elev= 30
  4366.9 1190.65  4392.7 1188.44  4476.2 1182.95    4673 1173.24  4737.4 1172.36
  4758.3 1170.23  4806.4 1171.19  4898.4 1170.16  4915.8 1170.58  4965.6 1169.01
  4983.4 1164.64  4983.9 1164.14  4989.6 1164.64  5015.7 1165.57  5022.6 1168.34
  5036.7 1169.52    5044  1168.5  5050.9 1169.68  5058.2  1166.7  5065.1 1168.13
  5072.4  1166.4  5079.2 1169.28  5093.4 1171.44  5326.9 1169.71  5631.2 1176.61
  5857.4 1187.38    6020  1192.6  6041.5 1194.16  6182.7 1199.26  6388.1 1213.08
#Mann= 7 ,-1 , 0
  4366.9     .05       0  4392.7     .12       0  4476.2     .05       0
  4806.4     .12       0  4898.4     .05       0  4983.4     .05       0
  4989.6     .05       0
Bank Sta=4983.4,4989.6
XS Rating Curve= 0 ,0
Exp/Cntr=0.3,0.1

Type RM Length L Ch R = 1 ,10201   ,788,788,788
BEGIN DESCRIPTION:
SANFERNANDO010 20.0
END DESCRIPTION:
XS GIS Cut Line= 3
      2781773.55     10219922.84      2782450.63     10219349.93
      2783205.66     10218353.15
#Sta/Elev= 30
  4203.1 1197.61  4246.6 1195.88  4275.1 1194.19  4282.9 1192.88  4303.7 1192.93
    4318 1190.46  4488.3 1182.33  4765.2 1172.84  4878.3 1170.21  4921.2 1167.16
  4970.6 1166.64  5002.6 1163.44  5003.1 1162.94  5008.8 1163.44  5034.3 1167.28
  5048.6 1168.14  5126.6 1168.06    5162 1166.74  5226.5 1167.15  5234.8 1168.01
  5255.6  1168.2  5334.6 1166.91  5434.5 1170.05  5455.3 1169.66  5512.6 1172.36
  5634.2 1175.17  5684.1 1177.52  5819.4 1181.54  6004.6 1188.89  6340.5 1206.21
#Mann= 3 ,-1 , 0
  4203.1     .05       0  5002.6     .05       0  5008.8     .05       0
Bank Sta=5002.6,5008.8
XS Rating Curve= 0 ,0
Exp/Cntr=0.3,0.1

Type RM Length L Ch R = 1 ,9413    ,413,413,413
BEGIN DESCRIPTION:
SANFERNANDO010 19.0
END DESCRIPTION:
XS GIS Cut Line= 3
      2782655.69      10220203.1       2782763.5       10219609.
      2783200.59     10218928.12
#Sta/Elev= 30
  4396.2 1186.14  4528.3 1180.59  4539.9 1181.26  4646.7 1177.96  4651.8 1178.36
  4731.6 1174.91  4751.9 1174.94  4772.2 1173.39  4817.1 1172.05  4923.9 1167.06
  4934.8 1167.67  4955.2 1165.21  4965.3 1165.77  4975.5 1165.25  4982.4 1163.48
  4992.1 1159.51  4992.6 1159.01  4998.7 1159.51  5013.1 1161.47  5028.3 1161.69
  5034.3 1163.28  5122.1 1166.68  5173.4 1166.07  5215.9 1164.23  5273.4 1165.45
  5382.4 1169.77    5434 1170.85  5506.1 1173.84  5600.4 1176.19  5809.1 1183.26
#Mann= 3 ,-1 , 0
  4396.2     .05       0  4992.1     .05       0  4998.7     .05       0
Bank Sta=4992.1,4998.7
XS Rating Curve= 0 ,0
Exp/Cntr=0.3,0.1

Type RM Length L Ch R = 1 ,9000    ,500,500,500
BEGIN DESCRIPTION:
SANFERNANDO010 18.0
END DESCRIPTION:
XS GIS Cut Line= 3
      2782805.68     10220053.11      2783148.99      10219669.9
      2783255.69      10219153.1
#Sta/Elev= 30
  4485.5 1181.92  4584.6 1180.01    4613 1178.27  4627.2 1178.23  4726.6 1171.12
  4867.9 1166.04  4896.3 1163.85  4910.5 1163.24  4917.2  1163.7  4931.4  1161.9
  4945.6 1162.15  4953.1 1160.97  4967.3 1160.41  4974.1 1160.86  4981.6 1159.77
  4988.3 1160.08  4991.2 1158.68  4991.7 1158.18  4997.3 1158.18  4997.8 1158.68
  5037.6 1160.39  5055.4 1164.14  5060.5 1163.39  5068.2 1163.69  5105.6 1162.19
  5119.2 1162.61  5292.8 1172.84  5364.3 1175.65    5402 1175.91  5527.7 1179.41
#Mann= 3 ,-1 , 0
  4485.5     .05       0  4991.2     .05       0  4997.8     .05       0
Bank Sta=4991.2,4997.8
XS Rating Curve= 0 ,0
Exp/Cntr=0.3,0.1

Type RM Length L Ch R = 1 ,8500    ,500,500,500
BEGIN DESCRIPTION:
SANFERNANDO010 17.0
END DESCRIPTION:
XS GIS Cut Line= 3
      2783255.69     10220153.11      2783620.88     10219742.52
      2783505.68     10219203.09
#Sta/Elev= 30
  4450.5    1181  4570.9    1176  4606.4 1172.27    4762 1165.87  4811.8 1163.02
  4818.8 1163.32  4825.5 1162.29  4861.5 1162.13    4925 1159.96  4939.2 1160.72
  4953.5 1160.28  4981.9 1158.65  4988.6 1157.34  4992.8 1155.41  4993.3 1154.91
  4999.5 1155.41  4999.8 1156.03  5002.7 1155.41  5019.8 1156.34  5040.3 1159.09
  5047.1  1160.8  5052.2 1159.81    5071 1163.15  5096.6 1165.46  5146.1 1166.98
  5190.5 1170.29  5195.6 1169.74  5289.5 1171.56  5383.4 1175.64  5551.6 1180.54
#Mann= 3 ,-1 , 0
  4450.5     .05       0  4992.8     .05       0  4999.5     .05       0
Bank Sta=4992.8,4999.5
XS Rating Curve= 0 ,0
Exp/Cntr=0.3,0.1

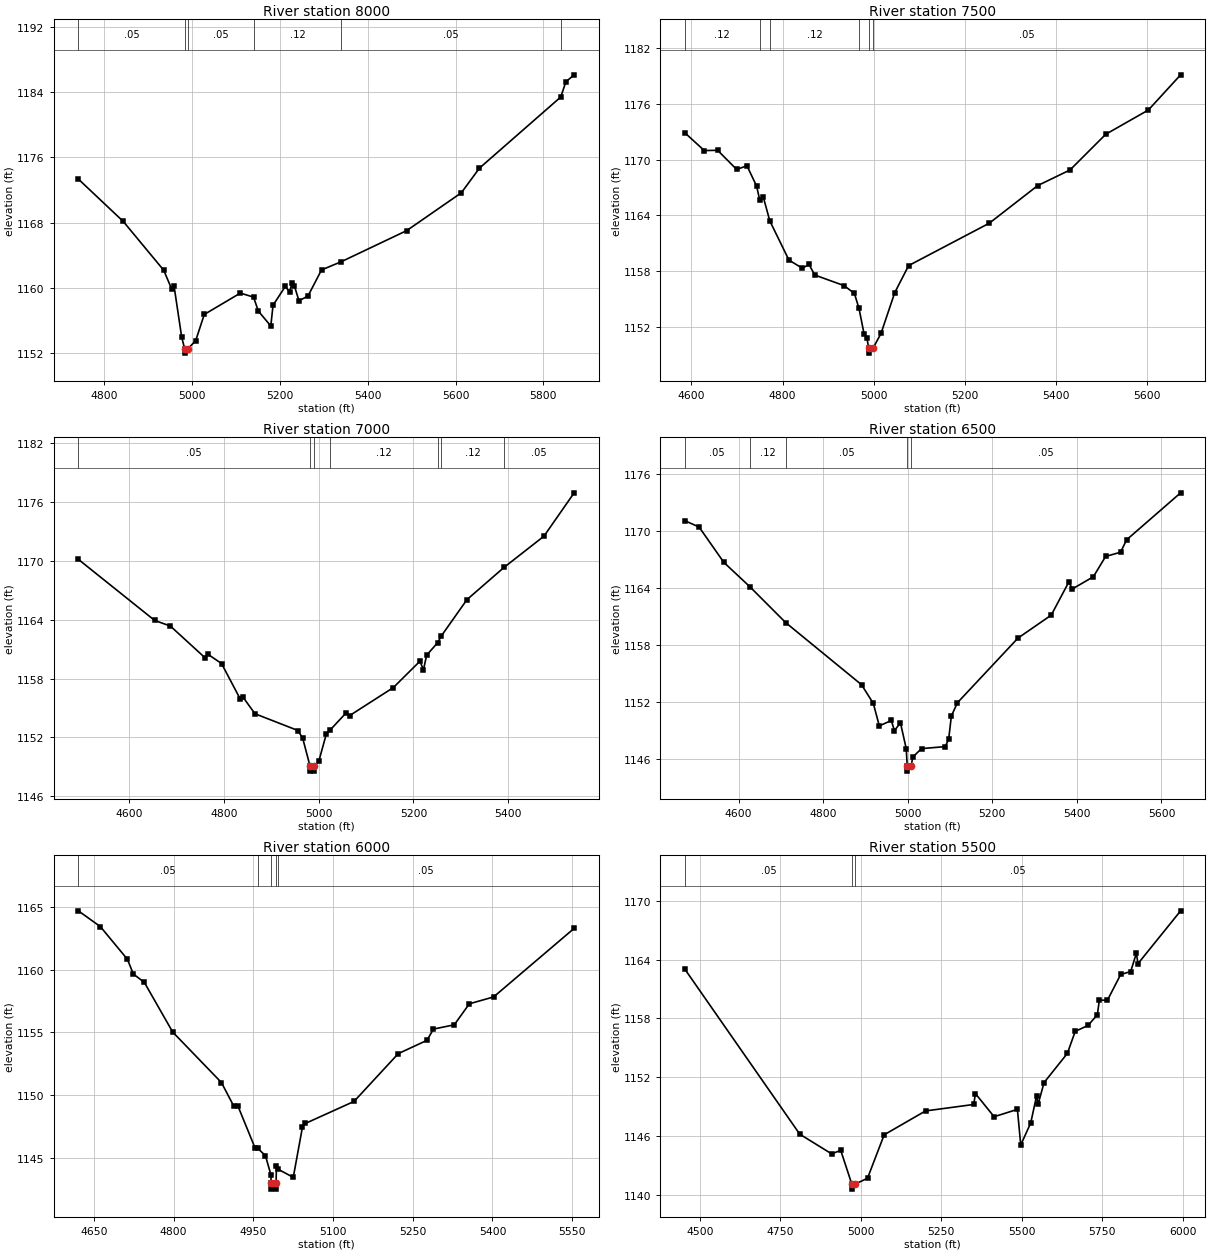
Type RM Length L Ch R = 1 ,8000    ,500,500,500
BEGIN DESCRIPTION:
SANFERNANDO010 16.0
END DESCRIPTION:
XS GIS Cut Line= 3
      2783955.68     10220303.15      2784009.59     10220050.64
      2784205.68     10219203.13
#Sta/Elev= 30
  4741.8 1173.35  4844.1 1168.15  4936.1 1162.17  4954.4 1159.84  4959.5 1160.27
    4977 1153.95  4983.9 1152.51  4984.4 1152.01  4990.6 1152.51  5008.9 1153.55
  5028.3 1156.75  5110.4 1159.37  5140.4 1158.88  5151.4 1157.16  5179.7 1155.34
  5184.8 1157.88    5213 1160.21  5222.4 1159.47  5227.5 1160.57  5233.5 1160.23
  5243.8 1158.43  5264.3 1159.01  5295.1 1162.21  5340.1 1163.22  5488.9 1167.03
  5613.3 1171.67  5654.4 1174.69  5839.4 1183.41  5851.1 1185.28  5869.9 1186.13
#Mann= 6 ,-1 , 0
  4741.8     .05       0  4983.9     .05       0  4990.6     .05       0
  5140.4     .12       0  5340.1     .05       0  5839.4     .12       0
Bank Sta=4983.9,4990.6
XS Rating Curve= 0 ,0
Exp/Cntr=0.3,0.1

Type RM Length L Ch R = 1 ,7500    ,500,500,500
BEGIN DESCRIPTION:
SANFERNANDO010 15.0
END DESCRIPTION:
XS GIS Cut Line= 3
       2784105.7      10220353.1       2784439.8     10220107.44
      2785105.68     10220003.11
#Sta/Elev= 30
  4585.3 1172.91  4628.1 1170.99  4657.4 1171.02  4699.1 1168.96  4721.8 1169.35
    4743 1167.16    4750 1165.62  4757.7 1165.98  4771.9 1163.42    4814 1159.19
  4843.3 1158.32    4858 1158.72  4870.8 1157.58  4935.2 1156.44  4957.7  1155.6
  4967.8 1153.99  4979.1  1151.2  4985.3 1150.77  4989.2 1149.67  4989.7 1149.17
  4998.3 1149.67  5016.1 1151.29  5046.4  1155.7  5076.8  1158.6    5254 1163.17
  5360.2 1167.22  5431.1  1168.9  5509.7 1172.75  5603.2 1175.36    5674 1179.15
#Mann= 6 ,-1 , 0
  4585.3     .12       0    4750     .05       0  4771.9     .12       0
  4967.8     .05       0  4989.2     .05       0  4998.3     .05       0
Bank Sta=4989.2,4998.3
XS Rating Curve= 0 ,0
Exp/Cntr=0.3,0.1

Type RM Length L Ch R = 1 ,7000    ,500,500,500
BEGIN DESCRIPTION:
SANFERNANDO010 14.0
END DESCRIPTION:
XS GIS Cut Line= 3
      2784205.73     10220453.12      2784709.32     10220519.15
      2785105.66     10220153.13
#Sta/Elev= 30
  4492.1 1170.15  4653.4 1163.92  4686.5 1163.35  4760.3 1160.09  4765.3 1160.49
  4794.6 1159.53    4834 1155.92  4839.1 1156.16  4865.2 1154.41    4956  1152.7
  4966.1 1151.91  4981.6 1149.06  4982.1 1148.56  4990.3 1148.56  4990.8 1149.06
    5000 1149.55  5015.9 1152.34  5024.4 1152.77  5058.4 1154.53  5065.2 1154.22
  5157.6 1157.08  5213.8 1159.77  5221.1 1158.88  5227.9 1160.38  5251.3 1161.66
  5258.3  1162.3    5313 1166.04  5391.4 1169.33  5475.7 1172.51  5539.5 1176.93
#Mann= 7 ,-1 , 0
  4492.1     .05       0  4981.6     .03       0  4990.8     .05       0
  5024.4     .12       0  5251.3     .05       0  5258.3     .12       0
  5391.4     .05       0
Bank Sta=4981.6,4990.8
XS Rating Curve= 0 ,0
Exp/Cntr=0.3,0.1

Type RM Length L Ch R = 1 ,6500    ,500,500,500
BEGIN DESCRIPTION:
SANFERNANDO010 13.0
END DESCRIPTION:
XS GIS Cut Line= 3
      2784655.66     10221303.13      2785010.01     10220912.91
      2785405.67     10220403.14
#Sta/Elev= 30
  4472.9 1171.09  4506.7 1170.42  4565.2  1166.7  4626.2 1164.16  4711.5 1160.36
  4890.9 1153.82  4918.7 1151.85  4932.8 1149.49  4961.2 1150.06  4968.6 1148.99
  4982.8 1149.82  4996.5 1147.09  4998.9 1145.23  4999.4 1144.73  5008.2 1145.23
  5011.7  1146.2  5032.6  1147.1  5088.7 1147.31  5096.8 1148.08  5103.2 1150.53
  5117.6 1151.93  5260.7 1158.73  5339.4 1161.15    5381 1164.64  5389.2  1163.9
    5439 1165.19  5467.9 1167.32  5503.2 1167.77  5517.7 1169.08  5645.3 1174.02
#Mann= 5 ,-1 , 0
  4472.9     .05       0  4626.2     .12       0  4711.5     .05       0
  4998.9     .05       0  5008.2     .05       0
Bank Sta=4998.9,5008.2
XS Rating Curve= 0 ,0
Exp/Cntr=0.3,0.1

Type RM Length L Ch R = 1 ,6000    ,500,500,500
BEGIN DESCRIPTION:
SANFERNANDO010 12.0
END DESCRIPTION:
XS GIS Cut Line= 3
      2785005.68     10221353.11      2785371.98     10221255.06
      2785605.69      10220753.1
#Sta/Elev= 30
  4620.8 1164.72  4662.2 1163.46  4713.1 1160.85  4724.3 1159.67    4745    1159
  4798.4 1155.03    4890    1151  4913.3 1149.11    4921 1149.13  4953.4 1145.76
  4958.5 1145.73  4972.8 1145.16  4983.1 1143.63  4983.5 1142.98    4984 1142.48
  4992.4 1142.48  4992.9 1142.98  4993.5 1144.33  4997.1 1144.06  5025.2 1143.42
  5042.5 1147.44    5048 1147.73  5139.6 1149.49  5222.8 1153.31  5276.8 1154.37
  5288.9 1155.27  5328.1 1155.61  5356.5 1157.29  5402.2 1157.84  5553.7 1163.32
#Mann= 5 ,-1 , 0
  4620.8     .05       0  4958.5     .12       0  4983.5     .05       0
  4992.9     .12       0  4997.1     .05       0
Bank Sta=4983.5,4992.9
XS Rating Curve= 0 ,0
Exp/Cntr=0.3,0.1

Type RM Length L Ch R = 1 ,5500    ,394,394,394
BEGIN DESCRIPTION:
SANFERNANDO010 11.0
END DESCRIPTION:
XS GIS Cut Line= 3
      2785055.67     10221953.12      2785545.86     10221709.69
      2786505.66     10221453.12
#Sta/Elev= 30
  4452.7 1163.03    4810  1146.2  4909.3 1144.19  4937.2 1144.56  4971.8  1141.1
  4972.3  1140.6  4981.2  1141.1  5020.5 1141.71  5072.3 1146.14  5200.7 1148.57
  5350.6 1149.23  5355.8 1150.34  5413.9 1147.98  5486.3 1148.73  5496.7  1145.1
  5527.7 1147.35  5545.7 1150.08  5550.9 1149.28  5569.1 1151.46  5641.6 1154.44
  5665.9 1156.68    5706 1157.29  5734.8 1158.38  5740.9 1159.88  5765.8 1159.84
  5807.2 1162.48  5838.3 1162.78  5855.9 1164.64  5861.1 1163.59  5993.5 1168.97
#Mann= 3 ,-1 , 0
  4452.7     .05       0  4971.8     .05       0  4981.2     .05       0
Bank Sta=4971.8,4981.2
XS Rating Curve= 0 ,0
Exp/Cntr=0.3,0.1

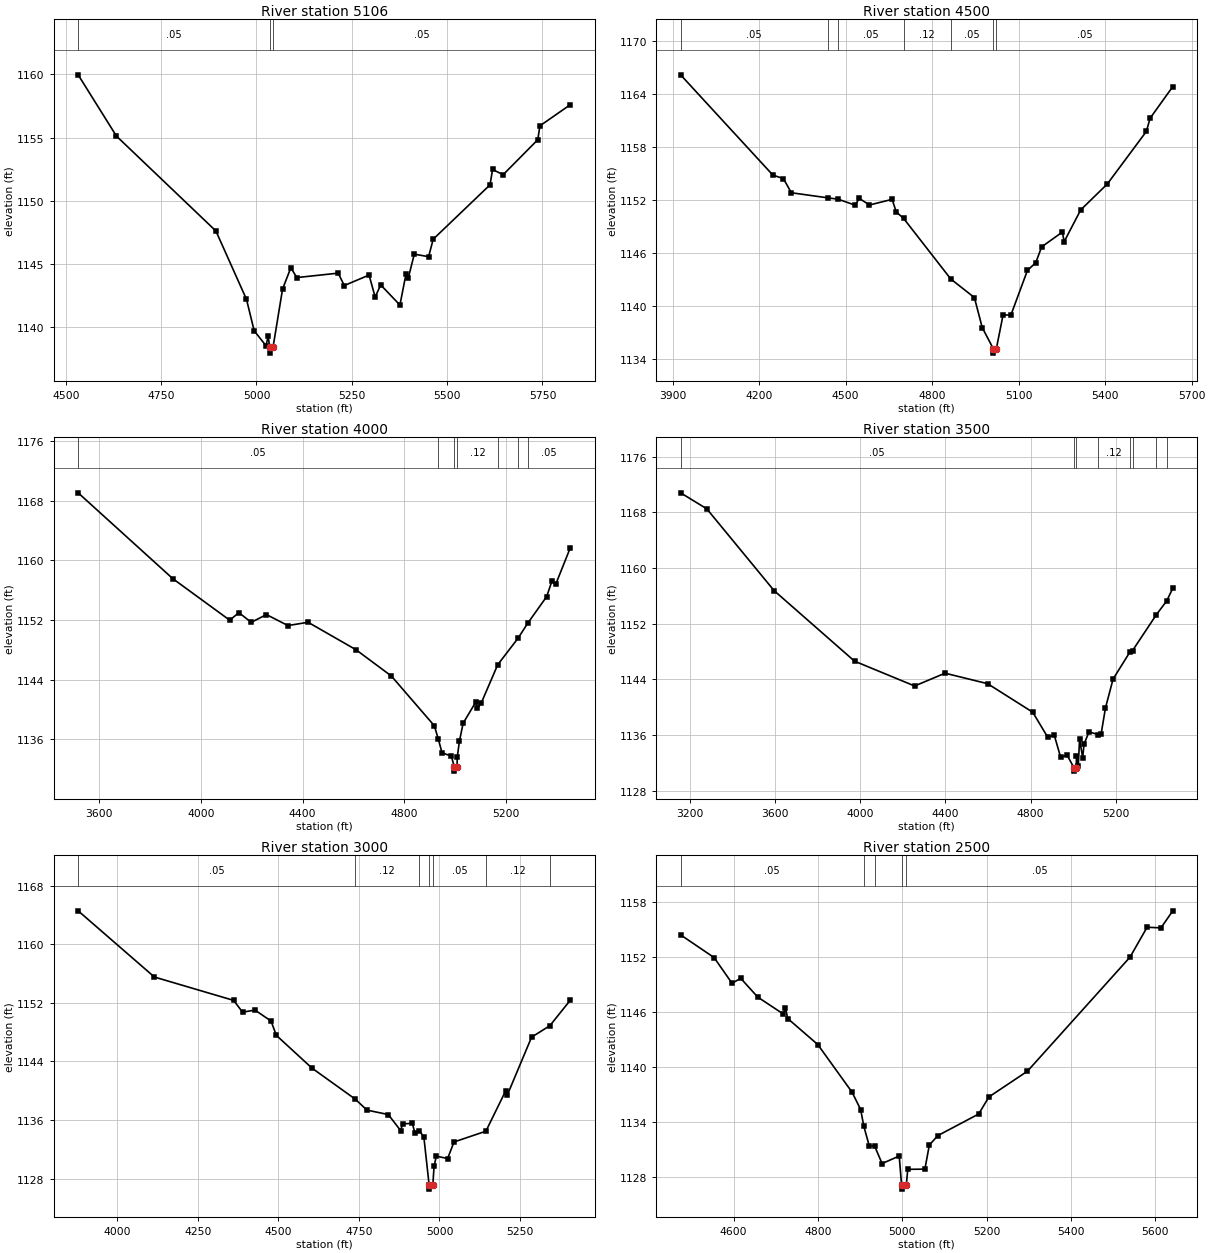
Type RM Length L Ch R = 1 ,5106    ,606,606,606
BEGIN DESCRIPTION:
SANFERNANDO010 10.0
END DESCRIPTION:
XS GIS Cut Line= 3
      2785105.67     10222053.11      2785571.75       10222092.
      2786289.15     10221688.48
#Sta/Elev= 30
  4532.3 1159.96  4632.7 1155.12  4893.6 1147.62  4973.8 1142.22  4993.9 1139.74
    5025 1138.55  5030.8 1139.33  5034.2 1138.47  5034.7 1137.97  5043.6 1138.47
  5068.4 1143.03    5090 1144.71    5106 1143.94  5214.3 1144.29  5230.3 1143.31
  5295.3 1144.14  5311.2  1142.4  5325.8 1143.36  5376.2 1141.77  5392.2 1144.23
  5397.9 1143.88  5413.9 1145.79  5451.5 1145.59  5463.4 1146.97  5612.6 1151.27
  5619.1 1152.48    5647 1152.07  5737.7 1154.83  5743.4 1155.93  5823.1  1157.6
#Mann= 3 ,-1 , 0
  4532.3     .05       0  5034.2     .05       0  5043.6     .05       0
Bank Sta=5034.2,5043.6
XS Rating Curve= 0 ,0
Exp/Cntr=0.3,0.1

Type RM Length L Ch R = 1 ,4500    ,500,500,500
BEGIN DESCRIPTION:
SANFERNANDO010 9.0
END DESCRIPTION:
XS GIS Cut Line= 3
      2785255.69     10222953.11      2786097.19     10222288.67
      2786505.66     10221803.14
#Sta/Elev= 30
  3927.8 1166.21  4247.6 1154.83  4284.5 1154.42  4311.7 1152.82  4438.5 1152.24
    4474 1152.09    4533 1151.41  4547.4 1152.18  4582.7 1151.43  4661.2 1152.07
  4675.7 1150.64  4701.1 1149.91  4864.9 1143.02  4946.6 1140.92  4973.8 1137.51
  5012.1 1135.11  5012.6 1134.61  5022.7 1135.11    5046 1138.94  5073.3 1138.94
  5130.6 1144.01  5159.2 1144.87    5180 1146.68  5251.5 1148.35    5258 1147.27
  5315.2 1150.87  5407.6 1153.82  5542.8 1159.78  5556.1 1161.29  5634.5 1164.87
#Mann= 7 ,-1 , 0
  3927.8     .05       0  4438.5     .12       0    4474     .05       0
  4701.1     .12       0  4864.9     .05       0  5012.1     .05       0
  5022.7     .05       0
Bank Sta=5012.1,5022.7
XS Rating Curve= 0 ,0
Exp/Cntr=0.3,0.1

Type RM Length L Ch R = 1 ,4000    ,500,500,500
BEGIN DESCRIPTION:
SANFERNANDO010 8.0
END DESCRIPTION:
XS GIS Cut Line= 3
      2785155.66     10223053.12      2786539.33     10222519.52
      2786805.69      10222153.1
#Sta/Elev= 30
    3517 1169.04  3889.5 1157.53  4113.2 1151.97  4149.4 1152.98  4197.8 1151.68
  4257.7 1152.72  4342.3 1151.25  4421.5 1151.69  4609.9 1148.01    4749 1144.49
  4918.1 1137.82  4933.7 1136.04  4948.1 1134.22  4985.4 1133.73  4996.7 1132.24
  4997.2 1131.74  5007.4 1132.24  5008.2 1133.59  5016.7 1135.74  5031.4 1138.16
  5081.6 1141.03  5087.8 1140.15  5102.5 1140.86  5167.4    1146  5247.3 1149.55
  5285.2 1151.55  5359.9 1155.13  5380.7 1157.22  5395.4 1156.77    5453 1161.68
#Mann= 7 ,-1 , 0
    3517     .05       0  4933.7     .12       0  4996.7     .07       0
  5007.4     .12       0  5167.4     .05       0  5247.3     .12       0
  5285.2     .05       0
Bank Sta=4996.7,5007.4
XS Rating Curve= 0 ,0
Exp/Cntr=0.3,0.1

Type RM Length L Ch R = 1 ,3500    ,500,500,500
BEGIN DESCRIPTION:
SANFERNANDO010 7.0
END DESCRIPTION:
XS GIS Cut Line= 3
      2785055.72     10223103.11      2786883.82     10222872.44
      2787155.69     10223253.13
#Sta/Elev= 30
  3157.4 1170.81  3280.3 1168.51  3596.3 1156.75  3973.8 1146.61    4256 1143.04
  4398.8 1144.88  4598.7 1143.37  4810.4 1139.27  4880.9 1135.67  4911.2 1136.01
  4941.4 1132.78  4971.6  1133.1  5003.8  1131.3  5004.3  1130.8    5015  1131.3
  5015.5 1132.97  5024.1 1131.49  5030.3 1135.38    5045 1132.72  5051.2 1134.68
  5074.5 1136.44  5118.7 1136.05  5131.1 1136.08  5151.9 1139.89  5187.6 1144.04
  5266.4 1147.91  5278.9 1148.13    5391  1153.3  5439.1 1155.26  5467.8 1157.09
#Mann= 8 ,-1 , 0
  3157.4     .05       0  5003.8     .03       0    5015     .05       0
  5118.7     .12       0  5266.4     .05       0  5278.9     .12       0
    5391     .05       0  5439.1     .12       0
Bank Sta=5003.8,5015
XS Rating Curve= 0 ,0
Exp/Cntr=0.3,0.1

Type RM Length L Ch R = 1 ,3000    ,500,500,500
BEGIN DESCRIPTION:
SANFERNANDO010 6.0
END DESCRIPTION:
XS GIS Cut Line= 3
      2785605.71      10223753.1      2786600.47     10223234.12
      2787005.68     10223203.11
#Sta/Elev= 30
    3878 1164.56  4114.8 1155.52  4360.9 1152.33  4388.6 1150.72  4427.1 1151.01
    4477 1149.51  4493.4 1147.56  4603.9 1143.09  4738.4 1138.85  4774.9 1137.35
  4841.2 1136.74  4879.7 1134.54  4885.4 1135.47  4915.7 1135.54  4923.9 1134.21
  4937.5 1134.55  4951.6 1133.66  4968.1 1127.06  4968.6 1126.56  4979.3 1127.06
  4983.3 1129.68  4990.2 1131.06  5025.3 1130.74  5045.3    1133  5144.2 1134.47
  5205.3 1139.95  5210.3 1139.36  5286.1 1147.31    5343 1148.88  5406.4 1152.36
#Mann= 7 ,-1 , 0
    3878     .05       0  4738.4     .12       0  4937.5     .05       0
  4968.1     .05       0  4979.3     .05       0  5144.2     .12       0
    5343     .05       0
Bank Sta=4968.1,4979.3
XS Rating Curve= 0 ,0
Exp/Cntr=0.3,0.1

Type RM Length L Ch R = 1 ,2500    ,500,500,500
BEGIN DESCRIPTION:
SANFERNANDO010 5.0
END DESCRIPTION:
XS GIS Cut Line= 3
      2786005.73      10223753.1      2786522.62     10223657.84
      2787155.72     10223553.11
#Sta/Elev= 30
  4474.4 1154.43  4553.9 1151.95  4596.4 1149.15    4617 1149.69  4657.4 1147.64
    4718  1145.8  4723.1 1146.42  4728.6  1145.3  4799.7 1142.47  4881.1 1137.27
  4901.4 1135.38    4909 1133.55  4921.8 1131.42  4934.3 1131.42  4952.3 1129.49
  4992.9 1130.31  4998.4  1127.2  4998.9  1126.7  5009.8  1127.2  5013.2 1128.86
  5053.8 1128.88  5064.3  1131.5  5084.2 1132.53  5181.3 1134.89  5205.8 1136.76
    5297 1139.56  5540.3    1152  5580.8 1155.26  5613.7 1155.19  5641.7 1157.05
#Mann= 5 ,-1 , 0
  4474.4     .05       0    4909     .12       0  4934.3     .05       0
  4998.4     .05       0  5009.8     .05       0
Bank Sta=4998.4,5009.8
XS Rating Curve= 0 ,0
Exp/Cntr=0.3,0.1

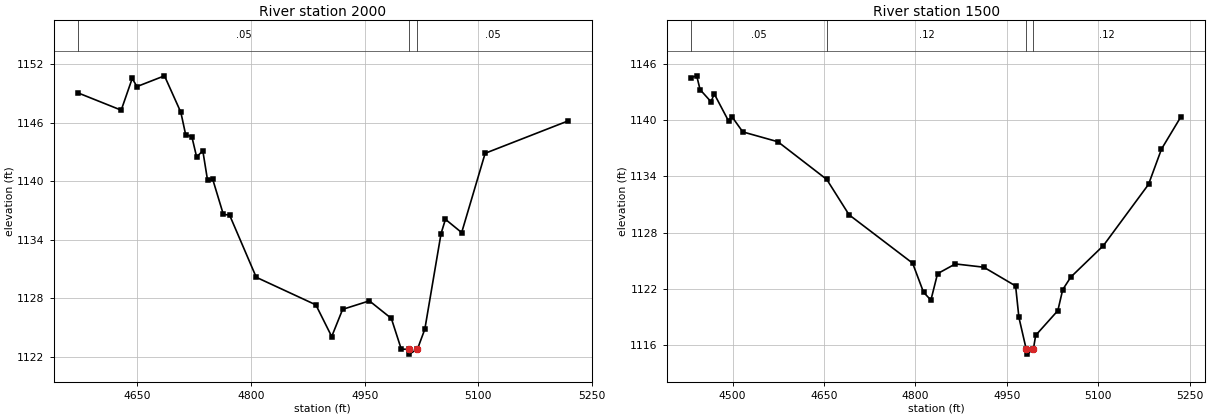
Type RM Length L Ch R = 1 ,2000    ,500,500,500
BEGIN DESCRIPTION:
SANFERNANDO010 4.0
END DESCRIPTION:
XS GIS Cut Line= 3
      2786555.66     10224253.13      2786893.53     10223989.76
      2787005.71     10223803.07
#Sta/Elev= 30
  4571.6 1149.04  4628.6 1147.27  4643.1 1150.52  4649.4 1149.69  4685.7 1150.79
  4707.3 1147.05  4713.7 1144.74  4721.8 1144.56  4728.1 1142.48  4736.3  1143.1
  4742.6 1140.06  4749.1 1140.25  4763.4 1136.58  4771.6 1136.52  4806.8 1130.14
  4885.5 1127.31  4906.4 1124.06  4920.8 1126.85  4956.1 1127.72  4985.1 1125.92
  4998.2 1122.77    5008 1122.76  5008.5 1122.26  5019.5 1122.76  5029.3 1124.82
  5050.7 1134.62  5056.5 1136.08  5077.9 1134.72  5108.9 1142.85  5217.8 1146.15
#Mann= 3 ,-1 , 0
  4571.6     .05       0    5008     .05       0  5019.5     .05       0
Bank Sta=5008,5019.5
XS Rating Curve= 0 ,0
Exp/Cntr=0.3,0.1

Type RM Length L Ch R = 1 ,1500    ,500,500,500
BEGIN DESCRIPTION:
SANFERNANDO010 3.0
END DESCRIPTION:
XS GIS Cut Line= 3
       2786755.7      10224503.1      2787275.58     10224274.79
      2787355.68     10224053.12
#Sta/Elev= 30
  4432.2 1144.54  4441.1 1144.72  4446.6 1143.25  4464.5 1141.96  4469.9 1142.79
  4493.3 1139.91  4498.8 1140.37  4516.7 1138.74  4574.3 1137.69  4654.5 1133.67
  4691.1  1129.9  4795.4 1124.74  4813.3 1121.64  4825.4  1120.8  4836.3 1123.62
  4865.5 1124.66  4912.2 1124.31  4964.4 1122.31  4969.8 1118.96  4981.9 1115.54
  4982.4 1115.04  4993.5 1115.54  4997.3 1117.04  5033.7 1119.68  5041.7 1121.92
    5055 1123.26  5108.4 1126.61  5182.5 1133.14  5203.8 1136.91  5235.7 1140.36
#Mann= 4 ,-1 , 0
  4432.2     .05       0  4654.5     .12       0  4981.9     .07       0
  4993.5     .12       0
Bank Sta=4981.9,4993.5
XS Rating Curve= 0 ,0
Exp/Cntr=0.3,0.1