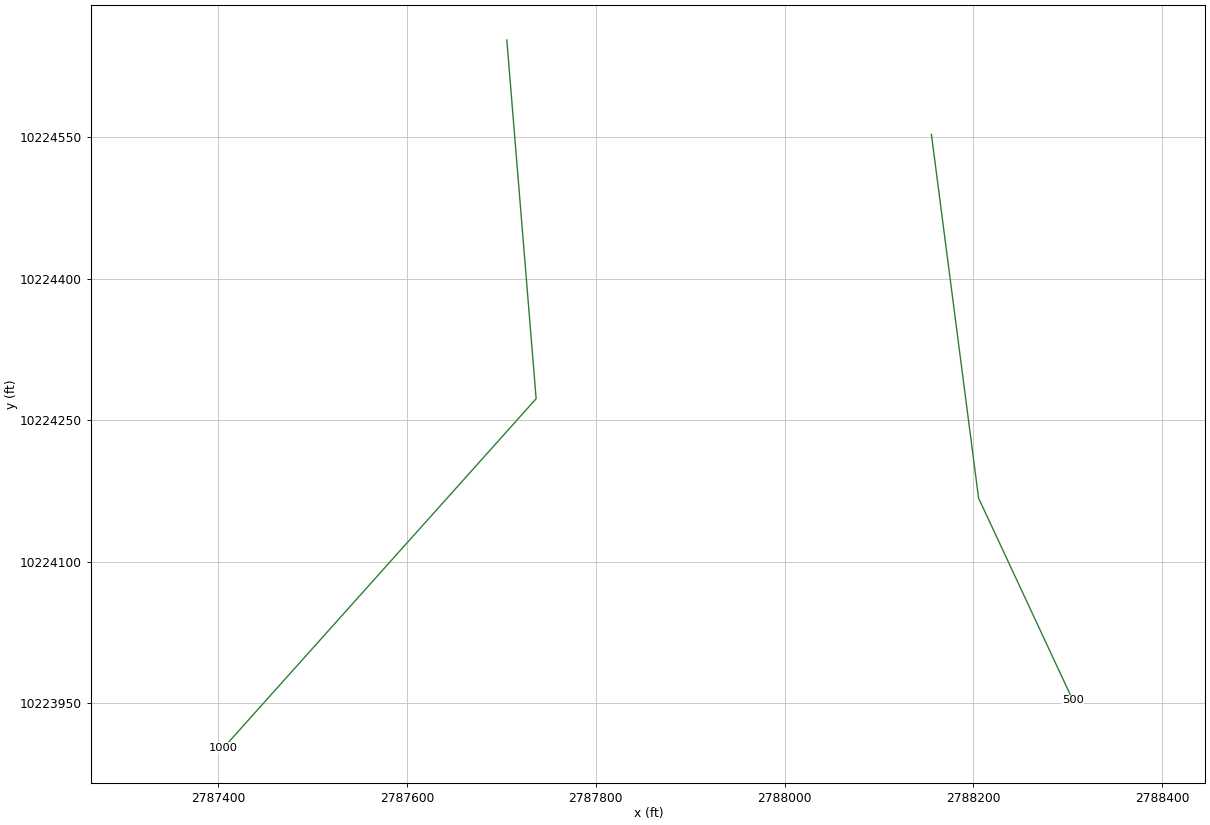
HEC-RAS study SANFERNANDO010.prj: SANFERNANDO010 Base Level Engineering

--- SANFERNANDO010.g01 (geometry) --- (continued)

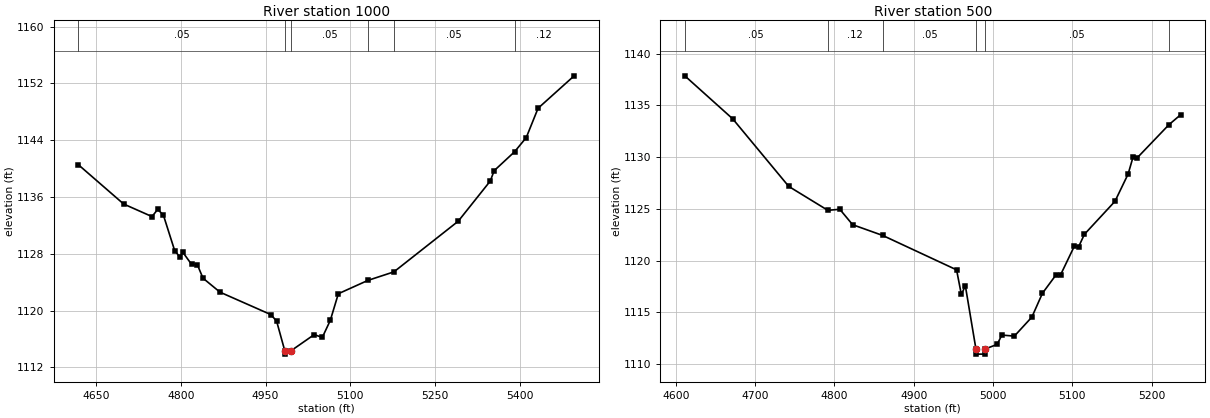
Type RM Length L Ch R = 1 ,1000    ,500,500,500
BEGIN DESCRIPTION:
SANFERNANDO010 2.0
END DESCRIPTION:
XS GIS Cut Line= 3
      2787705.69     10224653.08      2787736.76     10224272.85
      2787405.69     10223903.11
#Sta/Elev= 30
  4618.5 1140.56  4698.7 1135.02  4748.9 1133.25  4758.9 1134.25    4769 1133.48
    4789 1128.47  4798.4 1127.53  4803.4 1128.23  4819.1  1126.5  4829.2 1126.47
  4839.2 1124.57  4869.3  1122.6  4959.6 1119.43  4969.6  1118.5  4983.9 1114.37
  4984.4 1113.87  4995.5 1114.37  5036.1 1116.62  5050.4 1116.22  5064.6 1118.63
  5078.8 1122.38  5131.2 1124.26  5177.2 1125.46  5291.1  1132.6  5347.9 1138.27
  5354.6 1139.71  5390.8 1142.38  5411.5 1144.38  5432.4 1148.51  5496.3 1153.08
#Mann= 6 ,-1 , 0
  4618.5     .05       0  4983.9     .05       0  4995.5     .05       0
  5131.2     .12       0  5177.2     .05       0  5390.8     .12       0
Bank Sta=4983.9,4995.5
XS Rating Curve= 0 ,0
Exp/Cntr=0.3,0.1

Type RM Length L Ch R = 1 ,500     ,0,0,0
BEGIN DESCRIPTION:
SANFERNANDO010 1.0
END DESCRIPTION:
XS GIS Cut Line= 3
      2788155.69     10224553.08       2788205.7     10224167.51
       2788305.7     10223953.08
#Sta/Elev= 30
  4611.2 1137.85  4671.7 1133.69  4742.3 1127.17  4791.6 1124.86  4806.7 1124.96
  4822.9 1123.47  4860.9 1122.43    4954 1119.11    4960 1116.74  4965.1 1117.56
  4978.4 1111.47  4978.9 1110.97  4989.6 1110.97  4990.1 1111.47  5005.2 1111.91
  5011.1 1112.81  5026.9 1112.71    5049 1114.55  5062.3 1116.85  5079.7 1118.65
  5085.2 1118.63  5102.5 1121.39  5108.1 1121.36  5115.2 1122.54  5153.8 1125.73
  5170.4 1128.37  5176.6 1130.01  5182.2 1129.96    5222 1133.14  5236.6 1134.09
#Mann= 6 ,-1 , 0
  4611.2     .05       0  4791.6     .12       0  4860.9     .05       0
  4978.4     .05       0  4990.1     .05       0    5222     .12       0
Bank Sta=4978.4,4990.1
XS Rating Curve= 0 ,0
Exp/Cntr=0.3,0.1

Chan Stop Cuts=-1
Use User Specified Reach Order=0
Composite Channel Slope=5