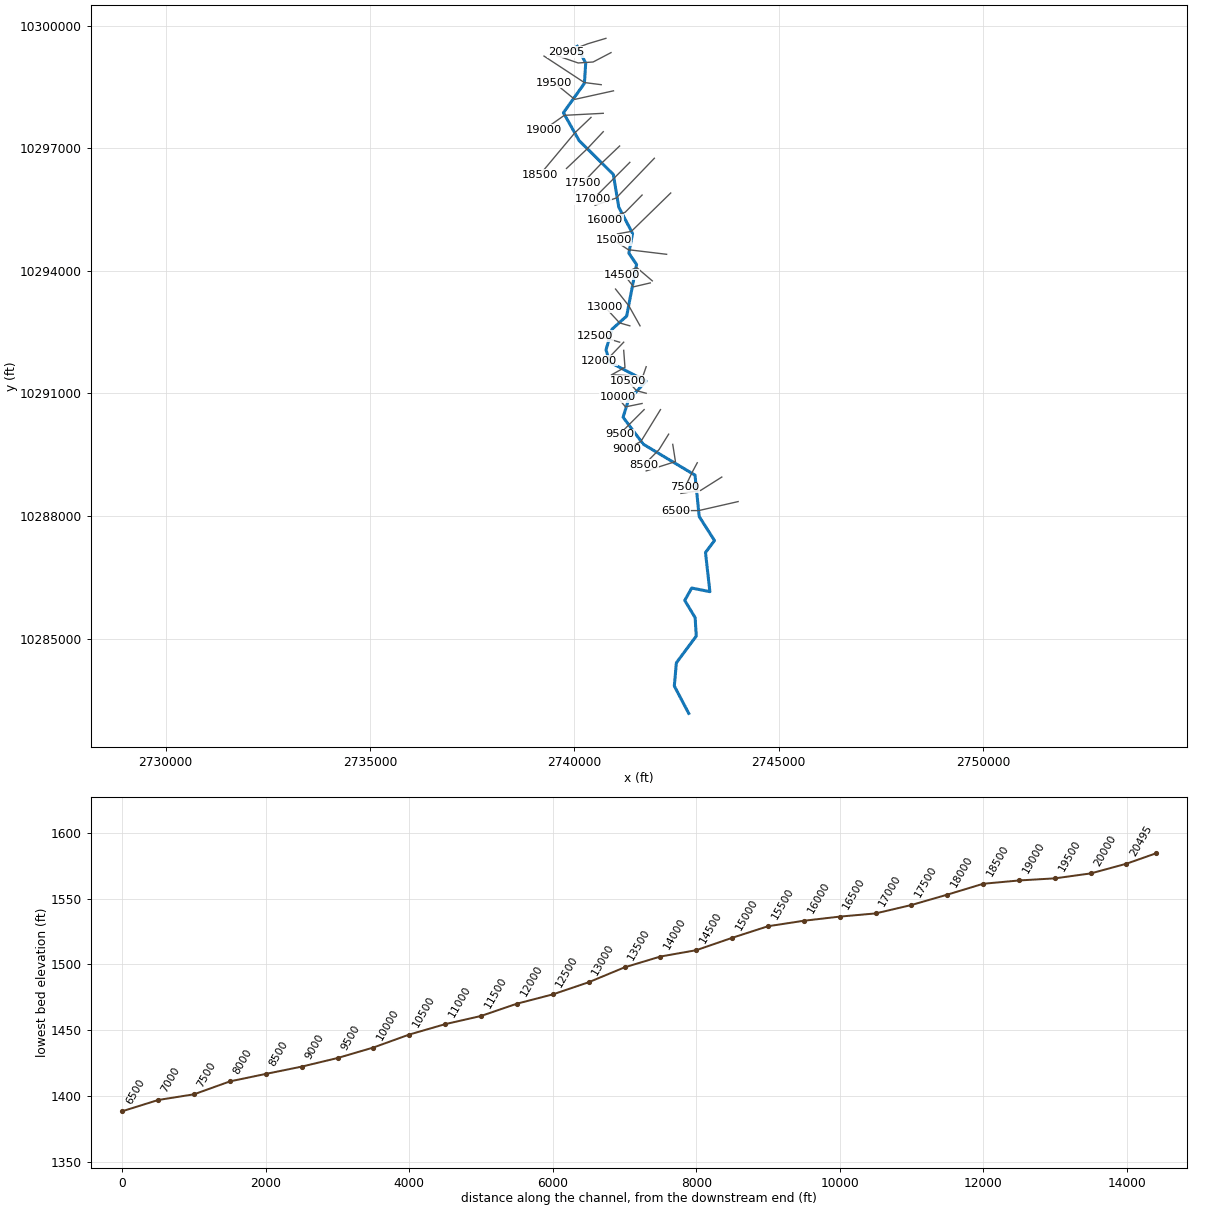
--- SANFERNANDO013.prj (project) ---

Proj Title=SANFERNANDO013 Base Level Engineering
Current Plan=p01
Default Exp/Contr=0.3,0.1
English Units
Geom File=g01
Flow File=f01
Plan File=p01
Y Axis Title=Elevation
X Axis Title(PF)=Main Channel Distance
X Axis Title(XS)=Station
BEGIN DESCRIPTION:
SANFERNANDO013
END DESCRIPTION:
DSS File=dss
DSS Export Rating Curves= 0
DSS Export Rating Curve Sorted= 0
DSS Export Volume Flow Curves= 0
DXF OffsetX= 0
DXF OffsetY= 0
DXF ScaleX= 1
DXF ScaleY= 10

--- SANFERNANDO013.p01 (plan) ---

Plan Title=Multiple Run
Program Version=4.10
Short Identifier=Multiple Run
Geom File=g01
Flow File=f01
Subcritical Flow
K Sum by GR= 0
Std Step Tol= 0.01
Critical Tol= 0.01
Num of Std Step Trials= 20
Max Error Tol= 0.3
Flow Tol Ratio= 0.001
Split Flow NTrial= 30
Split Flow Tol= 0.02
Split Flow Ratio= 0.02
Log Output Level= 0
Friction Slope Method= 1
Unsteady Friction Slope Method= 2
Unsteady Bridges Friction Slope Method= 1
Parabolic Critical Depth
Global Vel Dist= 1 , 1 , 1
Global Log Level= 0
CheckData=True
Encroach Param=-1 ,0,0, 0
BEGIN DESCRIPTION:
Multiple Run
END DESCRIPTION:
Computation Interval=1HOUR
Output Interval=1HOUR
Run HTab= 0
Run UNet= 0
Run PostProcess= 0
Run WQNet= 0
UNET Theta= 1
UNET Theta Warmup= 1
UNET ZTol= 0.02
UNET ZSATol= 0.05
UNET MxIter= 20
UNET MaxInSteps= 0
UNET DtIC= 0
UNET DtMin= 0
UNET MaxCRTS= 20
UNET WFStab= 2
UNET SFStab= 1
UNET WFX= 1
UNET SFX= 1
UNET DSS MLevel= 4
UNET DZMax Abort= 100
UNET Convert EG Bridges= 0
UNET Use Existing IB Tables=-1
UNET Froude Reduction=False
UNET Froude Limit= 1
UNET Froude Power= 10
UNET Time Slicing=0,0, 5
UNET Junction Losses=0
Instantaneous Interval=1HOUR
DSS File=dss
Write IC File= 0
Write IC File at Sim End=0
Echo Input=False
Echo Parameters=False
Echo Output=False
Write Detailed= 0
WQ AD Non Conservative
WQ ULTIMATE=-1
WQ Max Comp Step=1HOUR
WQ Output Interval=15MIN
WQ Output Selected Increments= 0
WQ Output face flow=0
WQ Output face velocity=0
WQ Output face area=0
WQ Output face dispersion=0
WQ Output cell volume=0
WQ Output cell surface area=0
WQ Output cell continuity=0
WQ Output cumulative cell continuity=0
WQ Output face conc=0
WQ Output face dconc_dx=0
WQ Output face courant=0
WQ Output face peclet=0
WQ Output face adv mass=0
WQ Output face disp mass=0
WQ Output cell mass=0
WQ Output cell source sink temp=0
WQ Output cell source sink nsm=0
WQ Output MaxMinRange=-1
WQ Daily Max Min Mean=-1
WQ Daily Range=0
WQ Daily Time=0
WQ Create Restart=0
WQ Fixed Restart=0
WQ System Summary=0
WQ Use Fixed Temperature=0
Sorting and Armoring Iterations= 10
XS Update Threshold= 0.02
Hydraulics Update Threshold= 0.02
Energy Slope Method= 1
Volume Change Method= 0
XS Weighting Method= 0
Number of US Weighted Cross Sections= 1
Number of DS Weighted Cross Sections= 1
Upstream XS Weight=0.25
Main XS Weight=0.5
Downstream XS Weight=0.25
Number of DS XS's Weighted with US Boundary= 1
Upstream Boundary Weight= 1
Weight of XSs Associated with US Boundary= 0
Number of US XS's Weighted with DS Boundary= 1
Downstream Boundary Weight= 0.5
Weight of XSs Associated with DS Boundary= 0.5
Sediment Output Level= 4
Mass or Volume Output= 0
Output Increment Type= 1
Profile and TS Output Increment= 10
XS Output Flag= 0
XS Output Increment= 10
Disregard all LS=0
Disregard all Conn=0
Disregard all Breaches=0
Disregard all Pumps=0

--- SANFERNANDO013.f01 (steady flow) ---

Flow Title=Multiple
Program Version=4.10
Number of Profiles= 7
Profile Names=10-year,25-year,50-year,1pct_min,100-year,1pct_plu,500-year
River Rch & RM=SANFERNANDO013,Reach-1         ,20905
     416     671     828     525    1090    2264    1481
River Rch & RM=SANFERNANDO013,Reach-1         ,13000
     664    1110    1580    1093    2154    4242    2986
River Rch & RM=SANFERNANDO013,Reach-1         ,7000
     985    1692    2462    1705    3409    6817    4731
Boundary for River Rch & Prof#=SANFERNANDO013,Reach-1         , 1
Up Type= 0
Dn Type= 3
Dn Slope=0.005
Boundary for River Rch & Prof#=SANFERNANDO013,Reach-1         , 2
Up Type= 0
Dn Type= 3
Dn Slope=0.005
Boundary for River Rch & Prof#=SANFERNANDO013,Reach-1         , 3
Up Type= 0
Dn Type= 3
Dn Slope=0.005
Boundary for River Rch & Prof#=SANFERNANDO013,Reach-1         , 4
Up Type= 0
Dn Type= 3
Dn Slope=0.005
Boundary for River Rch & Prof#=SANFERNANDO013,Reach-1         , 5
Up Type= 0
Dn Type= 3
Dn Slope=0.005
Boundary for River Rch & Prof#=SANFERNANDO013,Reach-1         , 6
Up Type= 0
Dn Type= 3
Dn Slope=0.005
Boundary for River Rch & Prof#=SANFERNANDO013,Reach-1         , 7
Up Type= 0
Dn Type= 3
Dn Slope=0.005
DSS Import GetInterval= 0
DSS Import GetPeak= 0
DSS Import FillOption= 0

--- SANFERNANDO013.g01 (geometry) ---

Geom Title=Existing Conditions
Program Version=4.10

River Reach=SANFERNANDO013  ,Reach-1
Reach XY= 30
      2740068.75       10299492.        2740276.       10299080.
        2740244.       10298586.        2739731.       10297867.
       2740113.5       10297187.      2740952.25       10296356.
       2741084.5       10295557.       2741422.5       10294915.
      2741331.75       10294431.        2741521.       10294153.
      2741277.75       10292891.      2740920.25       10292571.
      2740772.25       10292064.      2740866.75       10291762.
        2741753.       10291300.       2741319.5       10290832.
        2741191.       10290417.      2741686.75       10289756.
       2742950.5       10288999.       2743052.5       10287988.
      2743427.25       10287399.      2743206.75       10287108.
      2743314.25       10286149.      2742869.75       10286238.
      2742699.25       10285936.        2742953.       10285514.
       2742981.5       10285063.      2742494.25       10284408.
        2742444.       10283841.       2742796.5       10283171.

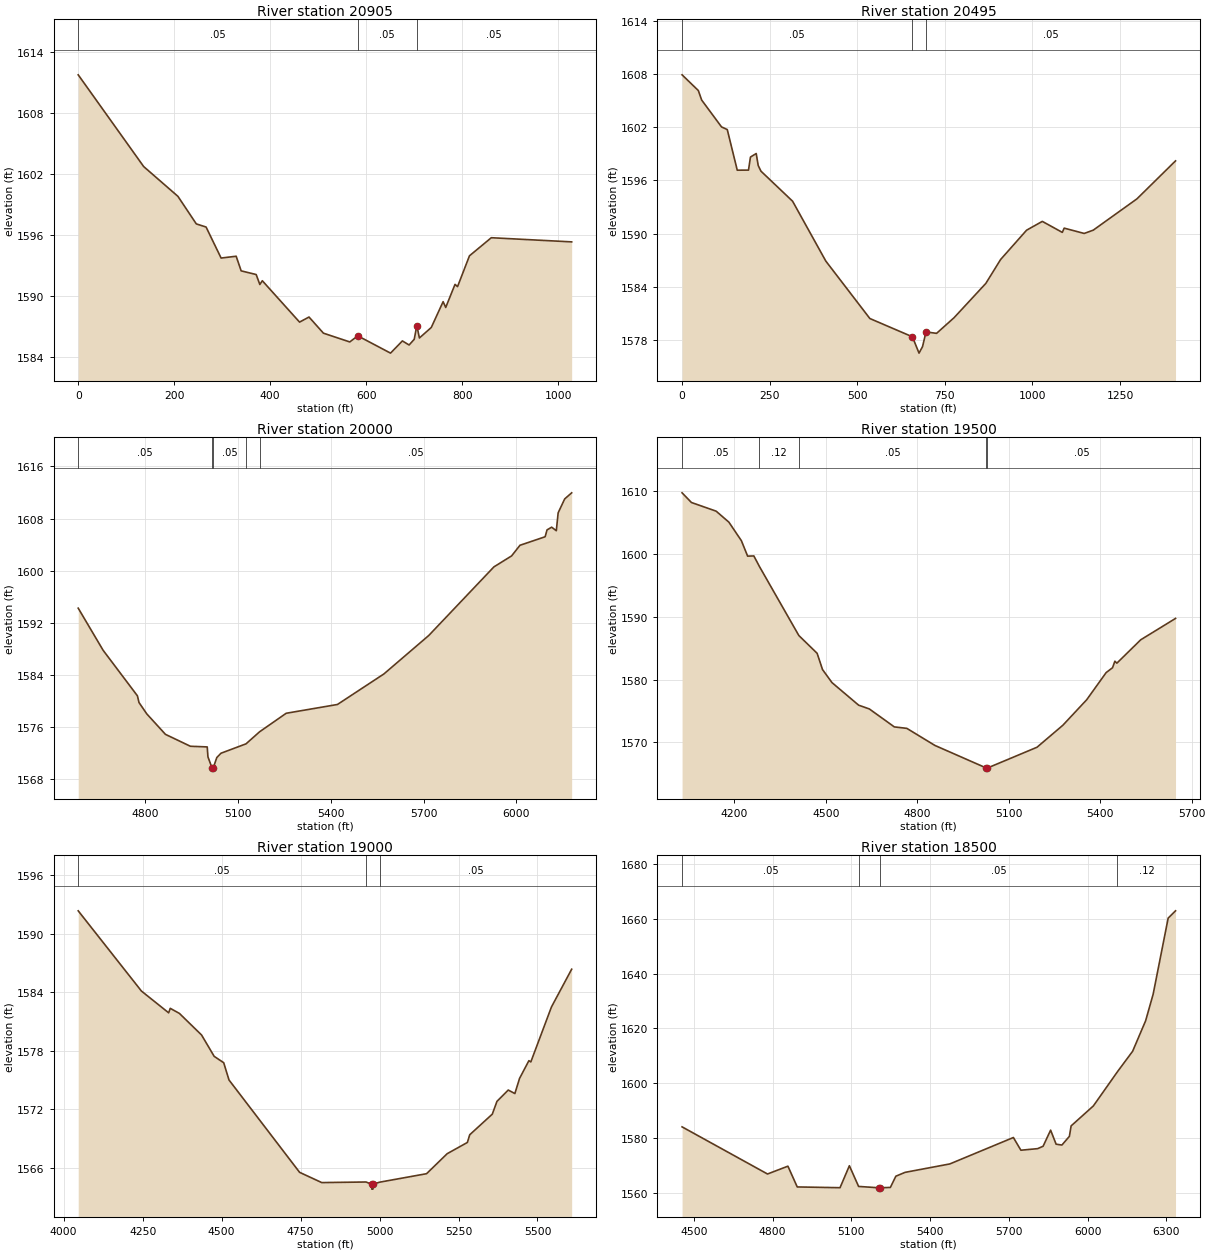
Type RM Length L Ch R = 1 ,20905   ,410,410,410
BEGIN DESCRIPTION:
SANFERNANDO013 41.0
END DESCRIPTION:
XS GIS Cut Line= 3
      2740771.01     10299687.34      2740327.57      10299554.6
      2739797.56      10299352.6
#Sta/Elev= 30
       0 1611.76   136.4 1602.74   207.8 1599.81   246.1  1597.1   266.5 1596.79
   297.8 1593.74   329.2 1593.92   339.6 1592.48   370.9 1592.12   378.5 1591.14
   383.7 1591.51   461.3 1587.44     481 1587.94   511.1 1586.35     566 1585.49
   582.6 1586.09   650.9 1584.39   675.6 1585.59   689.6 1585.19   700.3 1585.75
   705.7 1587.09   711.1 1585.88   735.8 1586.91   760.5 1589.45   765.9 1588.88
   785.3 1591.15   790.6 1590.93   815.4 1593.96   860.9 1595.74  1028.4 1595.33
#Mann= 3 , 0 , 0
       0     .05       0   582.6     .05       0   705.7     .05       0
Bank Sta=582.6,705.7
XS Rating Curve= 0 ,0
Exp/Cntr=0.3,0.1

Type RM Length L Ch R = 1 ,20495   ,495,495,495
XS GIS Cut Line= 4
      2740895.19     10299337.86      2740457.69     10299108.69
      2740091.37     10299084.39      2739574.01     10299263.21
#Sta/Elev= 30
       0 1607.89    46.4 1606.12    55.9 1605.05   112.6 1602.02     129 1601.72
   157.5 1597.14   189.6 1597.15   195.2 1598.62   211.6 1599.02   217.3 1597.67
   225.2 1597.03   315.5 1593.64   410.2  1586.9     536 1580.42   657.5 1578.36
   676.3 1576.52   686.3 1577.25   696.3 1578.91   726.4 1578.75   776.5 1580.52
     867 1584.38   909.3 1587.08   983.4 1590.38  1028.2 1591.37  1085.3 1590.13
  1090.6 1590.61  1147.7 1590.01  1173.5 1590.38  1298.3 1593.91  1408.4 1598.19
#Mann= 3 , 0 , 0
       0     .05       0   657.5     .05       0   696.3     .05       0
Bank Sta=657.5,696.3
XS Rating Curve= 0 ,0
Exp/Cntr=0.3,0.1

Type RM Length L Ch R = 1 ,20000   ,500,500,500
BEGIN DESCRIPTION:
SANFERNANDO013 40.0
END DESCRIPTION:
XS GIS Cut Line= 3
      2740655.73     10298553.11      2740241.61     10298606.16
      2739255.71     10299253.09
#Sta/Elev= 30
  4582.5 1594.23  4663.2 1587.75  4774.1 1580.76  4779.2 1579.73  4804.3 1577.99
  4864.8 1574.84  4945.5 1573.01    5000 1572.91  5002.3 1571.38  5015.4 1569.69
  5015.7 1569.19  5019.4 1569.69    5031 1571.28  5044.5 1571.94  5125.4 1573.38
  5169.6 1575.24  5255.5 1578.08  5421.3 1579.43  5571.9 1584.13  5716.6 1590.02
  5927.6 1600.57  5984.9 1602.26  6011.9 1603.89  6093.4  1605.2  6099.4 1606.25
  6114.4 1606.67  6129.5 1606.13  6135.5 1608.88  6156.6 1611.01  6179.2 1611.95
#Mann= 5 ,-1 , 0
  4582.5     .05       0  5015.4     .04       0  5019.4     .05       0
  5125.4     .12       0  5169.6     .05       0
Bank Sta=5015.4,5019.4
XS Rating Curve= 0 ,0
Exp/Cntr=0.3,0.1

Type RM Length L Ch R = 1 ,19500   ,500,500,500
BEGIN DESCRIPTION:
SANFERNANDO013 39.0
END DESCRIPTION:
XS GIS Cut Line= 3
      2740955.69     10298403.11      2740006.73     10298193.66
      2739505.66     10298603.13
#Sta/Elev= 30
  4028.2 1609.74  4058.9  1608.2    4140 1606.82  4181.8 1605.07  4222.8 1602.12
  4243.3 1599.66  4263.7 1599.69    4282 1598.01  4411.3 1587.02  4471.3 1584.19
    4489  1581.6  4520.1 1579.52  4607.5 1575.93  4642.6 1575.33  4724.6 1572.47
  4765.5 1572.24  4857.7 1569.52  5026.2 1565.93  5026.5 1565.43    5030 1565.43
  5030.2 1565.93  5192.6 1569.23  5277.4 1572.73  5355.6 1576.79  5419.5 1581.12
  5440.4 1581.89  5448.2 1582.93  5454.7 1582.62  5532.9 1586.34  5647.1 1589.74
#Mann= 5 ,-1 , 0
  4028.2     .05       0    4282     .12       0  4411.3     .05       0
  5026.2     .04       0  5030.2     .05       0
Bank Sta=5026.2,5030.2
XS Rating Curve= 0 ,0
Exp/Cntr=0.3,0.1

Type RM Length L Ch R = 1 ,19000   ,500,500,500
BEGIN DESCRIPTION:
SANFERNANDO013 38.0
END DESCRIPTION:
XS GIS Cut Line= 3
      2740705.65     10297853.11      2739752.94     10297803.34
       2739255.7     10297453.12
#Sta/Elev= 30
    4046 1592.33  4246.2 1584.11  4332.4 1581.88  4337.4 1582.34  4366.4 1581.82
  4436.5 1579.61  4476.5 1577.42  4506.6 1576.77  4523.4    1575  4746.9 1565.54
    4817 1564.49  4957.2 1564.55  4975.2 1564.32  4975.5 1563.82    4979 1563.82
  4979.2 1564.32    5000 1564.53  5148.8  1565.4  5214.1 1567.45    5278  1568.6
  5285.5 1569.39  5356.9  1571.5  5371.7 1572.81  5407.4 1573.97  5428.4 1573.61
  5443.2 1575.16  5472.8 1576.98  5478.9 1576.85  5544.2 1582.48  5608.2 1586.35
#Mann= 3 ,-1 , 0
    4046     .05       0  4957.2     .05       0    5000     .05       0
Bank Sta=4975.2,4979.2
XS Rating Curve= 0 ,0
Exp/Cntr=0.3,0.1

Type RM Length L Ch R = 1 ,18500   ,500,500,500
BEGIN DESCRIPTION:
SANFERNANDO013 37.0
END DESCRIPTION:
XS GIS Cut Line= 3
       2740405.7     10297753.12      2740012.11       10297377.
      2739155.65     10296353.07
#Sta/Elev= 30
  4455.6 1584.04    4781 1566.83  4858.7 1569.69  4894.2 1562.11  5057.2 1561.83
  5092.8 1569.85  5127.9 1562.29    5204 1561.81  5204.2 1561.31    5208 1561.81
  5248.9 1561.93  5269.8 1566.03  5304.9 1567.43  5475.4 1570.51  5717.4 1580.15
    5746 1575.51  5809.8 1576.09  5830.6 1576.97  5859.2 1582.84  5880.1 1577.71
  5902.2  1577.4  5930.7 1580.58  5937.3 1584.39    6022 1591.68  6113.9 1604.19
  6171.5 1611.63    6221 1622.76  6249.6 1632.43  6306.9 1660.24  6334.9  1662.9
#Mann= 4 ,-1 , 0
  4455.6     .05       0  5127.9     .05       0    5208     .05       0
  6113.9     .12       0
#Block Obstruct= 2 , 0
         5094.51 1571.37
Bank Sta=5204,5208
XS Rating Curve= 0 ,0
Exp/Cntr=0.5,0.3

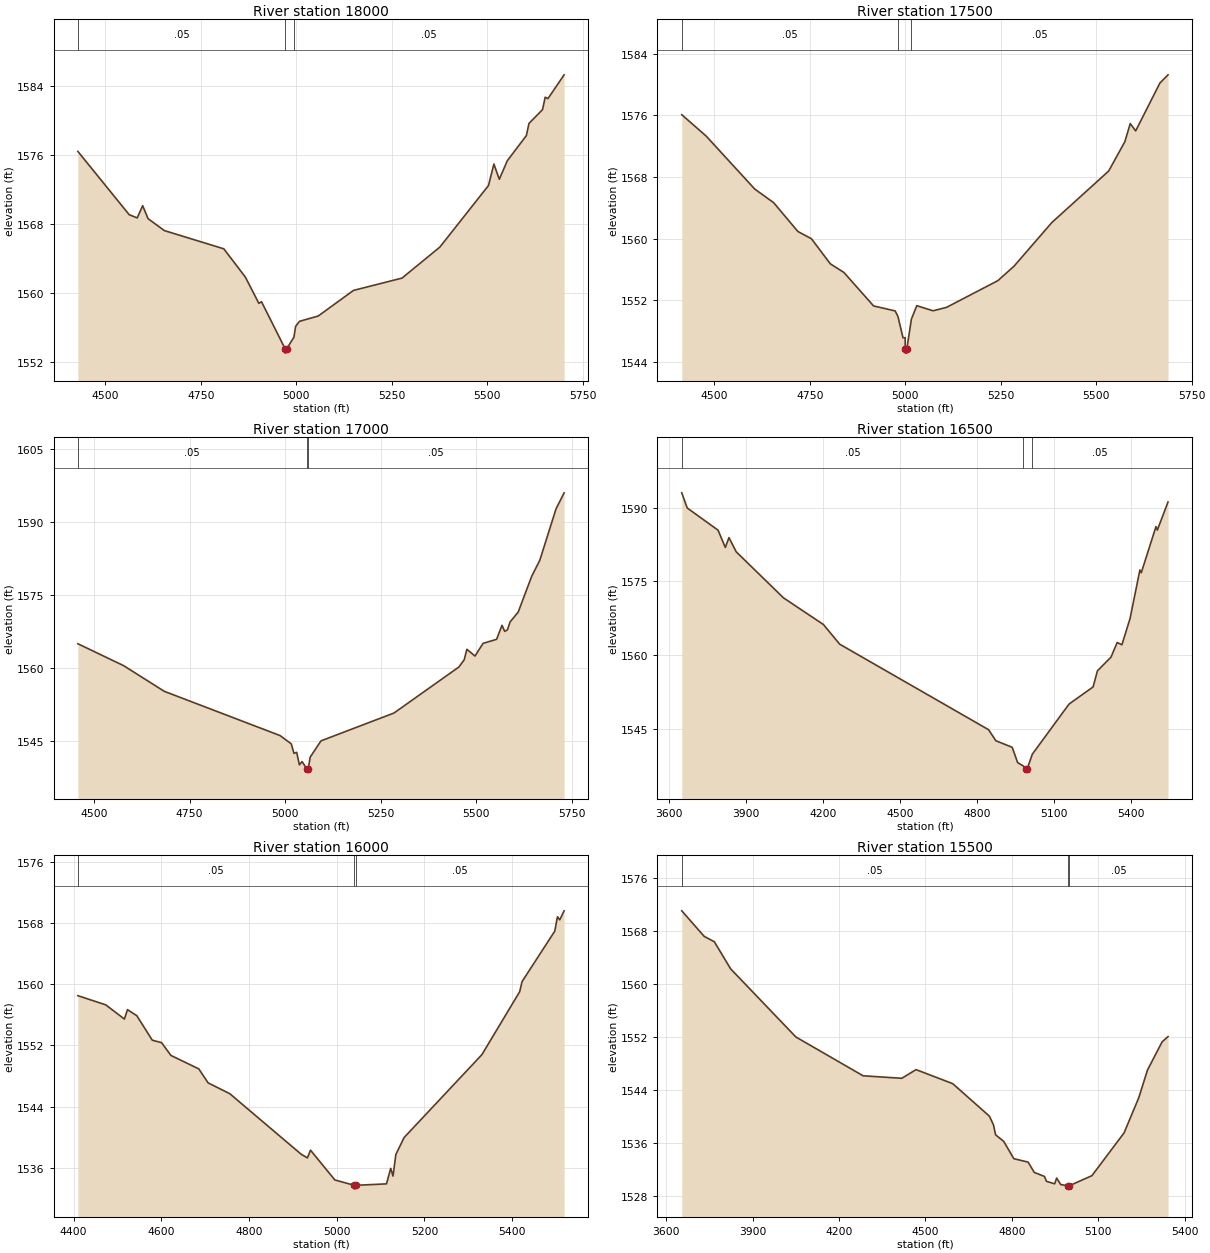
Type RM Length L Ch R = 1 ,18000   ,500,500,500
BEGIN DESCRIPTION:
SANFERNANDO013 36.0
END DESCRIPTION:
XS GIS Cut Line= 3
      2740705.65     10297403.08      2740314.66     10296985.85
      2739805.68      10296503.1
#Sta/Elev= 30
  4428.2 1576.46  4562.7 1569.11  4583.7 1568.74  4597.9 1570.16  4612.1 1568.65
  4654.6 1567.27  4810.4 1565.15  4866.7 1561.88  4902.2 1558.82  4909.1 1559.01
    4971 1553.54  4971.3 1553.04    4975 1553.54    4994 1554.89  4998.4 1556.14
  5008.4 1556.73  5057.7 1557.35  5149.9 1560.32    5277 1561.75  5376.1 1565.35
  5503.5  1572.5  5517.6 1574.99  5531.8 1573.23  5552.8 1575.38  5602.6 1578.29
  5609.5 1579.71    5645 1581.31  5651.9 1582.75  5659.2 1582.59  5701.5 1585.35
#Mann= 3 ,-1 , 0
  4428.2     .05       0    4971     .05       0    4994     .05       0
Bank Sta=4971,4975
XS Rating Curve= 0 ,0
Exp/Cntr=0.3,0.1

Type RM Length L Ch R = 1 ,17500   ,500,500,500
BEGIN DESCRIPTION:
SANFERNANDO013 35.0
END DESCRIPTION:
XS GIS Cut Line= 3
      2741105.72     10297053.14      2740682.33     10296649.45
      2740205.71     10296153.14
#Sta/Elev= 30
    4415 1576.07  4478.7 1573.31  4606.1 1566.43  4655.5 1564.67    4719 1560.93
  4754.6 1559.99  4803.9 1556.74  4839.5 1555.62  4917.2 1551.28  4973.8 1550.63
    4981 1549.91  4994.2 1547.16    5000 1547.16  5000.1 1545.66  5000.4 1545.16
  5003.9 1545.16  5004.1 1545.66  5016.3 1549.58  5030.4 1551.31  5072.9 1550.65
  5108.1 1551.09  5242.7 1554.56  5285.1 1556.44  5383.9 1562.09  5532.6 1568.76
  5575.1 1572.57  5589.2 1574.92  5603.4 1573.97  5666.9 1580.18  5688.1 1581.24
#Mann= 3 ,-1 , 0
    4415     .05       0    4981     .07       0  5016.3     .05       0
Bank Sta=5000.1,5004.1
XS Rating Curve= 0 ,0
Exp/Cntr=0.3,0.1

Type RM Length L Ch R = 1 ,17000   ,500,500,500
BEGIN DESCRIPTION:
SANFERNANDO013 34.0
END DESCRIPTION:
XS GIS Cut Line= 3
      2741355.71     10296653.14      2740972.84      10296268.8
      2740455.71     10295753.14
#Sta/Elev= 30
  4457.5 1564.99  4577.7 1560.46  4683.8 1555.19  4986.9 1546.08  5016.2 1544.37
  5023.2 1542.42  5030.3 1542.63  5037.4 1540.05  5044.4 1540.73  5056.6 1539.26
  5056.8 1538.76  5060.6 1539.26  5065.7 1541.65  5093.9 1544.99  5284.9 1550.72
  5454.6 1560.18  5468.7 1561.67  5475.8 1563.85    5497 1562.46  5518.2 1565.07
  5553.6  1565.9  5567.7 1568.78  5574.8 1567.54  5581.8 1567.82  5588.9 1569.48
  5610.1  1571.5  5645.5 1578.88  5666.7 1582.18  5709.1 1592.75  5730.3 1596.06
#Mann= 3 ,-1 , 0
  4457.5     .05       0  5056.6     .04       0  5060.6     .05       0
Bank Sta=5056.6,5060.6
XS Rating Curve= 0 ,0
Exp/Cntr=0.3,0.1

Type RM Length L Ch R = 1 ,16500   ,500,500,500
BEGIN DESCRIPTION:
SANFERNANDO013 33.0
END DESCRIPTION:
XS GIS Cut Line= 3
      2741955.72     10296753.15      2741020.45     10295779.61
      2740505.67     10295603.11
#Sta/Elev= 30
    3650 1593.03  3671.3 1589.94  3791.4 1585.42  3819.7 1581.91  3833.9  1583.9
  3862.2 1581.01  4046.1 1571.64  4201.8  1566.2  4265.3 1562.19  4845.2 1544.77
  4873.5 1542.53  4937.3 1541.18  4958.4 1538.07  4979.8  1537.4  4991.9 1536.83
  4992.2 1536.33  4995.9 1536.83  5015.6 1539.78  5158.6 1549.99  5252.4 1553.49
  5269.3 1556.77  5322.2 1559.56  5346.2 1562.54  5364.5 1562.07  5396.2  1567.4
  5434.7 1577.32    5440 1576.75  5497.3 1586.15  5502.6 1585.44  5544.2 1591.17
#Mann= 3 ,-1 , 0
    3650     .05       0  4979.8     .04       0  5015.6     .05       0
Bank Sta=4991.9,4995.9
XS Rating Curve= 0 ,0
Exp/Cntr=0.3,0.1

Type RM Length L Ch R = 1 ,16000   ,500,500,500
BEGIN DESCRIPTION:
SANFERNANDO013 32.0
END DESCRIPTION:
XS GIS Cut Line= 3
      2741655.68     10295853.11      2741242.24     10295432.06
       2740755.7     10295253.12
#Sta/Elev= 30
  4409.9 1558.52  4473.5 1557.32    4516 1555.46    4523 1556.69  4544.3  1555.9
  4579.6 1552.69  4600.8 1552.37    4622  1550.7  4685.7 1548.93  4706.9  1547.1
  4756.4 1545.68    4919 1537.76  4933.2 1537.28  4940.3 1538.29  4995.8 1534.39
  5040.3 1533.69  5040.6 1533.19  5044.3 1533.69  5113.5 1533.88  5123.1 1535.91
  5128.4  1534.9  5134.8 1537.72  5153.6 1539.94    5331  1550.8  5417.1 1559.04
  5422.5 1560.36  5497.1 1566.97  5503.2 1568.85  5508.5 1568.45  5518.4 1569.63
#Mann= 3 ,-1 , 0
  4409.9     .05       0  5040.3     .03       0  5044.3     .05       0
Bank Sta=5040.3,5044.3
XS Rating Curve= 0 ,0
Exp/Cntr=0.3,0.1

Type RM Length L Ch R = 1 ,15500   ,500,500,500
BEGIN DESCRIPTION:
SANFERNANDO013 31.0
END DESCRIPTION:
XS GIS Cut Line= 3
      2742355.72     10295903.14      2741392.25     10294963.65
      2741055.66     10294903.11
#Sta/Elev= 30
  3654.3 1571.02  3732.1 1567.17  3767.4 1566.35    3824 1562.26  4050.3 1551.98
  4283.6 1546.12  4418.1 1545.74  4467.5 1547.05  4594.8 1544.93  4722.2 1540.02
  4736.3 1538.69  4743.5 1537.21  4771.7 1536.22    4807  1533.6  4856.4 1533.09
  4877.8 1531.53    4913 1530.93  4920.2 1530.19  4948.5 1529.81  4955.5 1530.68
  4969.6  1529.7  4994.8 1529.51  4995.1 1529.01  4998.8 1529.51  5077.8 1531.04
  5189.6 1537.51  5240.4  1542.8  5270.8 1546.99  5321.6 1551.25    5342 1552.03
#Mann= 3 ,-1 , 0
  3654.3     .05       0  4994.8     .05       0  4998.8     .05       0
Bank Sta=4994.8,4998.8
XS Rating Curve= 0 ,0
Exp/Cntr=0.3,0.1

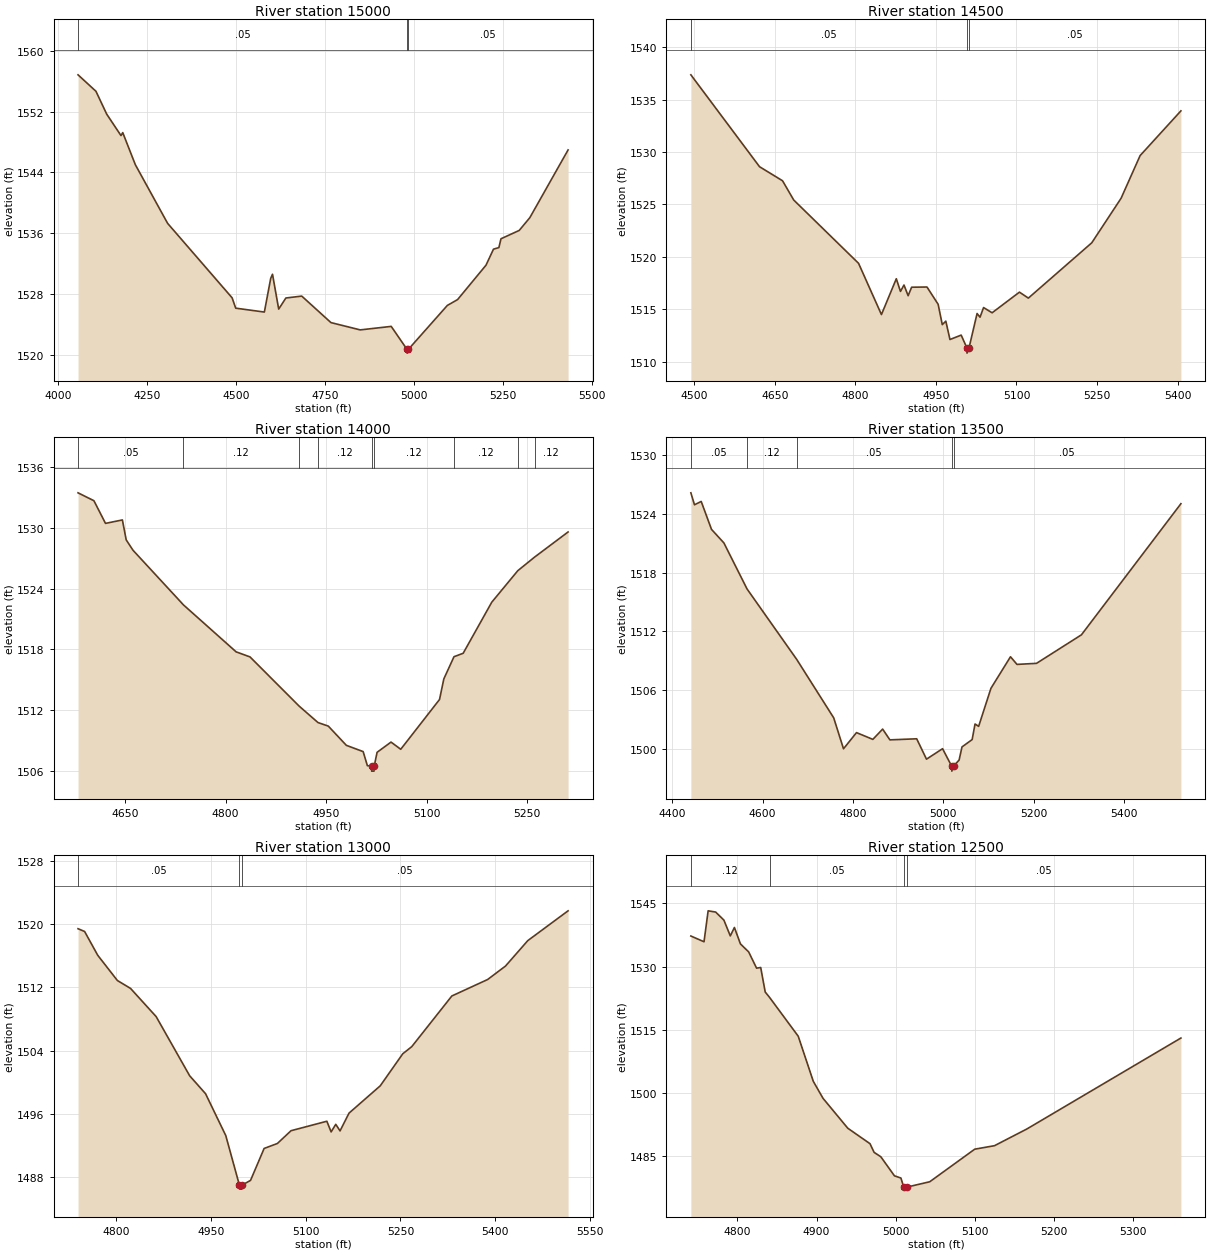
Type RM Length L Ch R = 1 ,15000   ,500,500,500
BEGIN DESCRIPTION:
SANFERNANDO013 30.0
END DESCRIPTION:
XS GIS Cut Line= 3
      2742255.68     10294403.11      2741319.03     10294515.77
      2740955.68     10294753.11
#Sta/Elev= 30
  4056.6 1556.85    4107 1554.68  4137.2 1551.67  4177.3 1548.85  4182.3 1549.24
  4217.7 1545.01  4308.4 1537.29  4489.7 1527.48  4499.8 1526.12  4580.3 1525.61
  4598.2 1530.05  4603.2 1530.59  4620.6    1526  4640.8 1527.46  4685.4 1527.71
  4767.5 1524.22  4849.7 1523.26  4936.9 1523.72  4981.2  1520.7  4981.5  1520.2
  4985.2  1520.7  5094.6 1526.48  5123.4 1527.25  5203.3 1531.78  5224.3 1533.89
  5239.5  1534.1  5245.4 1535.26  5296.7 1536.36  5326.5 1538.04    5434 1546.96
#Mann= 3 ,-1 , 0
  4056.6     .05       0  4981.2     .05       0  4985.2     .05       0
Bank Sta=4981.2,4985.2
XS Rating Curve= 0 ,0
Exp/Cntr=0.3,0.1

Type RM Length L Ch R = 1 ,14500   ,500,500,500
BEGIN DESCRIPTION:
SANFERNANDO013 29.0
END DESCRIPTION:
XS GIS Cut Line= 3
      2741905.65     10293753.14      2741520.42     10294081.82
      2741155.65      10293903.1
#Sta/Elev= 30
  4493.6 1537.36  4621.5 1528.59  4664.3 1527.25  4685.2 1525.41  4805.9 1519.37
  4848.5 1514.48  4876.2  1517.9  4883.9 1516.69  4890.5  1517.3  4898.2 1516.28
  4904.7 1517.09  4933.3 1517.11  4954.1 1515.46  4961.8 1513.52  4968.4 1513.85
  4976.1  1512.1    4997 1512.52  5007.6  1511.3  5007.9  1510.8  5011.6  1511.3
  5026.6 1514.58  5032.1 1514.23  5038.7 1515.15  5054.6 1514.65  5105.5 1516.62
  5122.1 1516.05  5240.2 1521.33  5294.8 1525.58  5330.2 1529.65  5406.2 1533.92
#Mann= 3 ,-1 , 0
  4493.6     .05       0  5007.6     .05       0  5011.6     .05       0
Bank Sta=5007.6,5011.6
XS Rating Curve= 0 ,0
Exp/Cntr=0.3,0.1

Type RM Length L Ch R = 1 ,14000   ,500,500,500
BEGIN DESCRIPTION:
SANFERNANDO013 28.0
END DESCRIPTION:
XS GIS Cut Line= 3
      2741855.64      10293703.1      2741446.43     10293607.18
      2741255.71     10293853.08
#Sta/Elev= 30
  4579.7 1533.48  4603.4  1532.7  4620.7 1530.46  4645.9  1530.8  4651.6 1528.83
  4661.8  1527.8  4737.1  1522.4  4815.7 1517.76  4836.4 1517.26  4909.7  1512.4
  4937.9 1510.77  4953.3 1510.42  4980.2 1508.52  5005.3  1507.9  5011.6 1506.51
  5017.8 1506.47    5018 1505.97  5021.5 1505.97  5021.8 1506.47  5026.1 1507.83
  5046.9 1508.84  5061.4 1508.13  5119.3 1513.05  5125.7 1515.08  5140.9 1517.28
  5154.6 1517.62  5197.3 1522.67  5236.1 1525.78  5261.1 1527.12  5311.2 1529.61
#Mann= 9 ,-1 , 0
  4579.7     .05       0  4737.1     .12       0  4909.7     .05       0
  4937.9     .12       0  5017.8     .07       0  5021.8     .12       0
  5140.9     .12       0  5236.1     .05       0  5261.1     .12       0
Bank Sta=5017.8,5021.8
XS Rating Curve= 0 ,0
Exp/Cntr=0.3,0.1

Type RM Length L Ch R = 1 ,13500   ,500,500,500
BEGIN DESCRIPTION:
SANFERNANDO013 27.0
END DESCRIPTION:
XS GIS Cut Line= 3
      2741605.69     10292653.09      2741332.68     10293140.77
      2741005.66     10293553.14
#Sta/Elev= 30
  4441.1 1526.14  4449.1 1524.92    4464 1525.26  4486.8 1522.41  4514.2 1521.03
  4565.5 1516.33  4675.5 1509.14  4757.4 1503.18  4779.1 1500.02  4807.9 1501.67
  4844.1 1500.98  4865.8 1502.03  4881.8 1500.93  4941.2 1501.04  4962.9 1498.96
  4998.5 1500.03  5018.7 1498.24    5019 1497.74  5022.7 1498.24  5035.1 1498.87
  5041.5 1500.21    5064 1500.96  5070.4 1502.55  5078.4 1502.31  5105.6 1506.19
  5148.9 1509.41  5163.3 1508.63  5206.6 1508.74    5306 1511.65  5526.3 1525.03
#Mann= 5 ,-1 , 0
  4441.1     .05       0  4565.5     .12       0  4675.5     .05       0
  5018.7     .05       0  5022.7     .05       0
Bank Sta=5018.7,5022.7
XS Rating Curve= 0 ,0
Exp/Cntr=0.3,0.1

Type RM Length L Ch R = 1 ,13000   ,500,500,500
BEGIN DESCRIPTION:
SANFERNANDO013 26.0
END DESCRIPTION:
XS GIS Cut Line= 3
      2741355.65     10292653.12      2741105.18     10292724.35
      2740755.67     10293103.13
#Sta/Elev= 30
  4739.6 1519.45    4750  1519.1  4770.8 1516.08  4801.9 1512.88  4822.7 1511.88
  4863.3  1508.3  4916.3  1500.8  4941.5 1498.52  4973.5 1493.21  4995.1 1486.92
  4995.4 1486.42  4998.9 1486.42  4999.1 1486.92  5012.7 1487.53  5034.2 1491.58
  5055.2 1492.21  5076.8 1493.83  5133.5 1495.03  5140.3 1493.68  5147.6 1494.64
  5154.4 1493.81  5168.6 1496.06    5218 1499.52  5253.7 1503.59  5267.9 1504.49
  5331.4 1510.92  5388.1 1513.01  5416.4 1514.72  5451.6 1517.94  5515.4 1521.72
#Mann= 3 ,-1 , 0
  4739.6     .05       0  4995.1     .05       0  4999.1     .05       0
Bank Sta=4995.1,4999.1
XS Rating Curve= 0 ,0
Exp/Cntr=0.3,0.1

Type RM Length L Ch R = 1 ,12500   ,500,500,500
BEGIN DESCRIPTION:
SANFERNANDO013 25.0
END DESCRIPTION:
XS GIS Cut Line= 3
      2741105.65     10292253.12      2740857.68     10292326.85
      2740505.65     10292403.12
#Sta/Elev= 30
  4741.3 1537.26  4757.9  1535.9  4763.1 1543.24  4772.6 1542.95    4783 1541.04
  4791.1 1537.29  4796.3 1539.29  4803.9 1535.39  4814.3 1533.49  4824.3 1529.63
  4829.5 1529.79  4835.2 1523.97  4840.7 1522.69  4876.9 1513.48  4895.9 1502.78
  4908.2 1498.74  4939.5 1491.64  4967.5 1487.98  4972.7 1485.92  4981.2 1484.87
  4998.4 1480.35  5006.6 1479.82  5010.1 1477.69  5010.4 1477.19  5014.5 1477.69
    5043 1478.94  5099.8 1486.67  5124.8  1487.5  5165.8 1491.48  5360.2 1513.05
#Mann= 4 ,-1 , 0
  4741.3     .12       0  4840.7     .05       0  5010.1     .05       0
  5014.5     .05       0
Bank Sta=5010.1,5014.5
XS Rating Curve= 0 ,0
Exp/Cntr=0.3,0.1

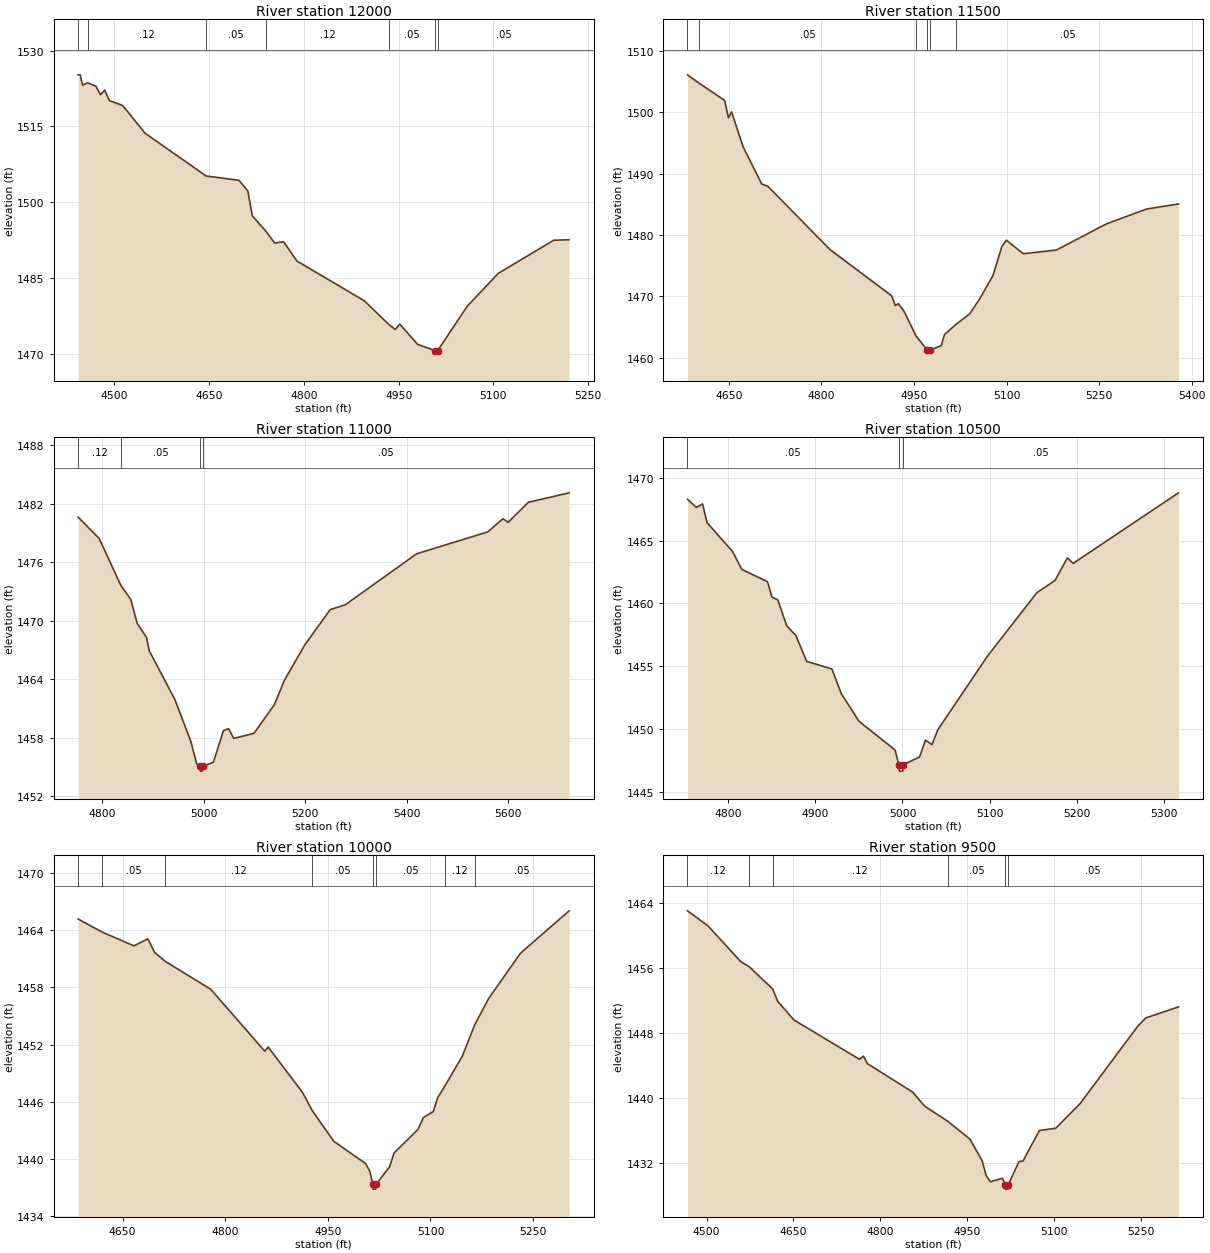
Type RM Length L Ch R = 1 ,12000   ,500,500,500
BEGIN DESCRIPTION:
SANFERNANDO013 24.0
END DESCRIPTION:
XS GIS Cut Line= 3
      2741205.66     10292253.08      2740820.44     10291850.07
      2740605.72     10291803.12
#Sta/Elev= 30
  4442.5  1525.2  4445.9  1525.2  4449.5 1523.17  4457.7 1523.61  4470.6 1522.97
  4477.8 1521.27  4484.8 1522.18    4492  1520.1  4513.1 1519.13  4548.6 1513.64
  4645.2 1505.18  4697.1 1504.33  4711.2 1502.22  4718.4 1497.27  4739.8 1494.25
  4753.7 1491.91  4767.8 1492.16  4788.9 1488.35  4895.2 1480.51  4934.8 1475.74
  4944.6 1474.81  4951.8 1475.85  4980.1 1471.85  5007.3 1470.62  5007.6 1470.12
  5011.8 1470.62  5058.6 1479.42  5107.6  1485.9  5195.3 1492.46  5219.8 1492.56
#Mann= 7 ,-1 , 0
  4442.5     .05       0  4457.7     .12       0  4645.2     .05       0
  4739.8     .12       0  4934.8     .05       0  5007.3     .05       0
  5011.8     .05       0
Bank Sta=5007.3,5011.8
XS Rating Curve= 0 ,0
Exp/Cntr=0.3,0.1

Type RM Length L Ch R = 1 ,11500   ,500,500,500
BEGIN DESCRIPTION:
SANFERNANDO013 23.0
END DESCRIPTION:
XS GIS Cut Line= 3
      2741205.68     10292053.15      2741236.57      10291637.3
      2740905.68     10291453.11
#Sta/Elev= 30
    4583 1506.08  4602.2  1504.7  4643.2 1501.92  4649.4 1499.08  4654.4 1500.04
  4673.3 1494.33  4703.4  1488.3  4713.4 1487.93  4813.7 1477.66    4914  1470.1
  4919.7 1468.51  4924.8 1468.84    4934 1467.58  4953.4 1463.56  4971.9 1461.28
  4972.2 1460.78  4976.4 1461.28  4994.2    1462  4999.6 1463.83  5018.8 1465.51
  5040.3 1467.17  5056.3 1469.56    5078 1473.39  5092.6 1478.16  5099.7 1479.16
  5127.2 1476.96  5180.9 1477.56  5262.1 1481.83  5327.2 1484.24  5378.7 1485.06
#Mann= 6 ,-1 , 0
    4583     .12       0  4602.2     .05       0  4953.4     .12       0
  4971.9     .07       0  4976.4     .12       0  5018.8     .05       0
Bank Sta=4971.9,4976.4
XS Rating Curve= 0 ,0
Exp/Cntr=0.3,0.1

Type RM Length L Ch R = 1 ,11000   ,500,500,500
BEGIN DESCRIPTION:
SANFERNANDO013 22.0
END DESCRIPTION:
XS GIS Cut Line= 3
      2741755.67     10291653.08      2741674.59     10291419.24
      2740955.69     10291453.11
#Sta/Elev= 30
  4752.5 1480.64  4793.9 1478.46  4836.8 1473.62  4856.2  1472.2  4868.9 1469.73
  4887.3 1468.29  4892.6 1466.92    4943 1461.93  4974.7  1457.6    4986 1455.32
  4993.1 1455.06  4993.4 1454.56  4997.3 1454.56  4997.6 1455.06  5018.9 1455.46
  5038.9 1458.72    5049 1458.92    5059 1457.92    5099 1458.44  5139.1 1461.38
  5159.1  1463.9  5199.1 1467.52  5249.2 1471.14  5279.2 1471.65  5419.4 1476.87
  5559.5 1479.12  5589.6 1480.47  5599.6  1480.1  5639.6 1482.16  5719.7 1483.13
#Mann= 4 ,-1 , 0
  4752.5     .12       0  4836.8     .05       0  4993.1     .05       0
  4997.6     .05       0
Bank Sta=4993.1,4997.6
XS Rating Curve= 0 ,0
Exp/Cntr=0.3,0.1

Type RM Length L Ch R = 1 ,10500   ,500,500,500
BEGIN DESCRIPTION:
SANFERNANDO013 21.0
END DESCRIPTION:
XS GIS Cut Line= 3
      2741755.65     10291003.12      2741517.53     10291067.61
      2741305.66     10291303.14
#Sta/Elev= 30
  4753.3 1468.29  4763.6 1467.63  4770.6 1467.92  4775.8 1466.42  4805.1 1464.13
  4815.6 1462.71  4845.1 1461.73  4850.3  1460.5  4856.9 1460.29  4867.2 1458.22
  4877.6 1457.46  4890.1 1455.39    4919 1454.79    4930  1452.8  4950.1 1450.63
  4991.5 1448.34    4996 1447.16  4996.4 1446.66  5000.4 1446.66  5000.7 1447.16
  5019.7 1447.79  5026.4 1449.13  5033.9 1448.77  5040.6 1449.95  5097.4 1455.79
  5154.2 1460.85  5175.1 1461.83  5189.3 1463.62    5196 1463.19  5316.8  1468.8
#Mann= 3 ,-1 , 0
  4753.3     .05       0    4996     .05       0  5000.7     .05       0
Bank Sta=4996,5000.7
XS Rating Curve= 0 ,0
Exp/Cntr=0.3,0.1

Type RM Length L Ch R = 1 ,10000   ,500,500,500
BEGIN DESCRIPTION:
SANFERNANDO013 20.0
END DESCRIPTION:
XS GIS Cut Line= 3
      2741655.65      10290753.1      2741248.92     10290670.17
      2741055.65     10290903.15
#Sta/Elev= 30
  4584.9 1465.19  4619.4 1463.84  4666.5 1462.37  4686.9  1463.1  4697.1 1461.66
  4712.5 1460.73  4778.8 1457.81  4857.7 1451.31  4862.8 1451.74  4913.4 1446.93
  4927.1 1445.07  4958.8 1441.83  5005.2  1439.5  5011.6 1438.64  5015.8 1437.31
  5016.1 1436.81  5020.1 1436.81  5020.5 1437.31  5040.3 1439.16  5046.8 1440.61
  5081.9 1443.09  5089.7 1444.33  5104.1 1444.95  5110.6 1446.42  5121.3 1447.66
  5146.7 1450.79  5164.9  1454.1  5185.2 1456.85  5231.7  1461.6  5302.7 1466.05
#Mann= 8 ,-1 , 0
  4584.9     .12       0  4619.4     .05       0  4712.5     .12       0
  4927.1     .05       0  5015.8     .05       0  5020.5     .05       0
  5121.3     .12       0  5164.9     .05       0
Bank Sta=5015.8,5020.5
XS Rating Curve= 0 ,0
Exp/Cntr=0.3,0.1

Type RM Length L Ch R = 1 ,9500    ,500,500,500
BEGIN DESCRIPTION:
SANFERNANDO013 19.0
END DESCRIPTION:
XS GIS Cut Line= 3
      2741705.69     10290603.12       2741328.4     10290226.64
      2741105.71     10290003.14
#Sta/Elev= 30
    4467 1462.98  4502.4 1461.14  4558.9 1456.75    4573 1456.16  4614.3 1453.38
  4622.6 1451.89  4650.9 1449.58    4764 1444.75  4771.1 1445.13  4778.1  1444.2
  4855.9 1440.73  4877.1 1438.98  4916.4 1437.15  4954.9 1434.96  4976.1 1432.31
  4983.2 1430.46  4990.3  1429.7  5011.5 1430.14  5016.1  1429.3  5016.5  1428.8
  5020.7  1428.8    5021  1429.3  5039.8 1432.17  5046.9 1432.26  5075.1    1436
  5103.4 1436.28  5145.8 1439.33  5244.8 1448.78    5259 1449.83  5315.5 1451.18
#Mann= 6 ,-1 , 0
    4467     .12       0    4573     .05       0  4614.3     .12       0
  4916.4     .05       0  5016.1     .05       0    5021     .05       0
Bank Sta=5016.1,5021
XS Rating Curve= 0 ,0
Exp/Cntr=0.3,0.1

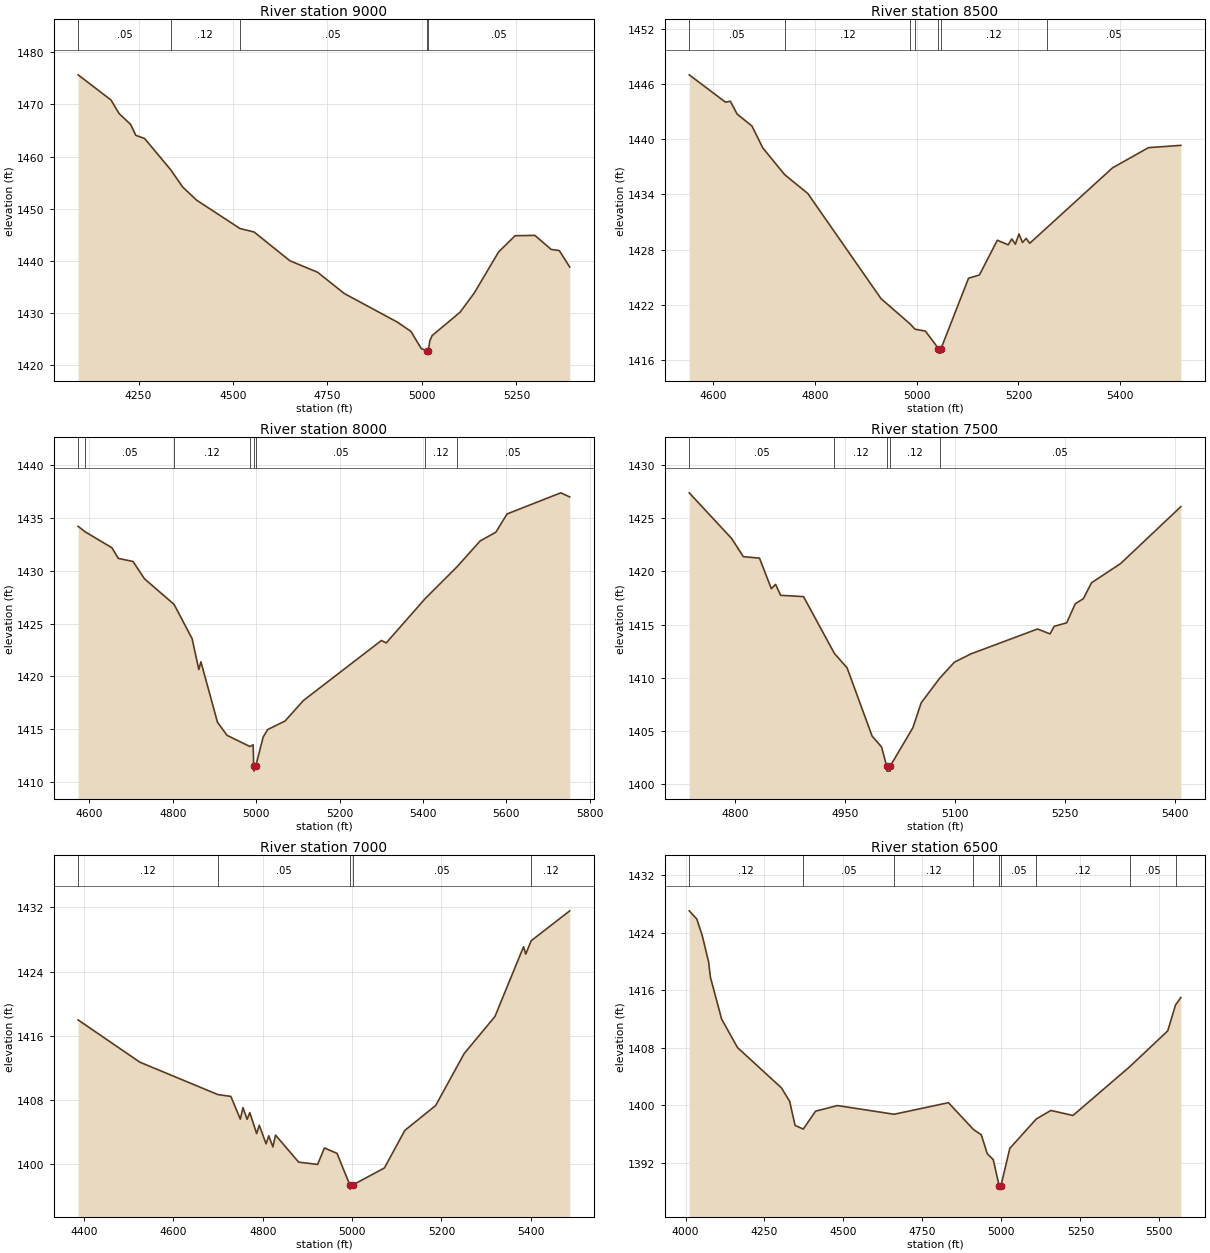
Type RM Length L Ch R = 1 ,9000    ,500,500,500
BEGIN DESCRIPTION:
SANFERNANDO013 18.0
END DESCRIPTION:
XS GIS Cut Line= 3
       2742105.7     10290603.13        2741629.      10289828.1
      2741290.56      10289632.1
#Sta/Elev= 30
  4090.1 1475.68  4177.1 1470.85  4198.4 1468.26  4229.2 1466.15  4242.7 1464.07
  4265.9 1463.47  4334.8 1457.49  4366.5 1454.18  4403.2 1451.65  4518.5 1446.18
  4555.8 1445.52  4650.5    1440  4723.9 1437.79  4794.5 1433.71  4934.5 1428.24
  4970.6 1426.46  4998.4 1423.13  5012.3 1422.77  5012.7 1422.27  5017.2 1422.77
  5020.5 1424.56  5026.9 1425.63  5100.9 1430.12  5138.2 1433.78  5202.8 1441.68
  5246.5  1444.8  5298.9 1444.87    5342 1442.17  5363.5 1441.95  5391.1 1438.79
#Mann= 5 ,-1 , 0
  4090.1     .05       0  4334.8     .12       0  4518.5     .05       0
  5012.3     .05       0  5017.2     .05       0
Bank Sta=5012.3,5017.2
XS Rating Curve= 0 ,0
Exp/Cntr=0.3,0.1

Type RM Length L Ch R = 1 ,8500    ,500,500,500
BEGIN DESCRIPTION:
SANFERNANDO013 17.0
END DESCRIPTION:
XS GIS Cut Line= 3
      2742305.67     10290003.09      2742069.53     10289623.56
      2741705.72     10289253.14
#Sta/Elev= 30
    4553    1447  4624.4 1444.02  4633.8 1444.13  4647.2 1442.73  4676.3 1441.43
  4697.6 1439.05  4740.6 1436.14  4786.1 1434.09  4929.9 1422.66  4987.8 1419.87
  4996.8 1419.33  5017.1 1419.13  5042.9 1417.23  5043.3 1416.73  5047.5 1416.73
  5047.9 1417.23    5102 1424.88  5123.3 1425.23  5158.6 1429.01  5179.9 1428.51
  5186.9 1429.15    5194 1428.58    5201 1429.69  5208.1 1428.76  5215.2 1429.21
  5222.3 1428.68    5257 1430.43  5384.9 1436.88  5455.6 1439.08  5519.2 1439.33
#Mann= 7 ,-1 , 0
    4553     .05       0  4740.6     .12       0  4987.8     .05       0
  4996.8     .12       0  5042.9     .07       0  5047.9     .12       0
    5257     .05       0
Bank Sta=5042.9,5047.9
XS Rating Curve= 0 ,0
Exp/Cntr=0.3,0.1

Type RM Length L Ch R = 1 ,8000    ,500,500,500
BEGIN DESCRIPTION:
SANFERNANDO013 16.0
END DESCRIPTION:
XS GIS Cut Line= 3
      2742405.68     10289753.14      2742471.87     10289331.61
      2741755.64      10289103.1
#Sta/Elev= 30
  4573.3 1434.22  4590.1  1433.7  4654.3 1432.19  4669.8 1431.18  4704.9 1430.89
  4732.4 1429.25  4803.3 1426.83  4846.6 1423.58  4862.6 1420.66  4867.7 1421.39
  4907.4 1415.67  4930.3 1414.43  4985.1 1413.37  4992.9 1413.53  4994.2 1411.54
  4994.6 1411.04  4999.2 1411.54    5017 1414.28  5027.5 1414.97  5069.5 1415.79
  5113.5 1417.73  5300.4 1423.41  5311.9 1423.18  5405.6 1427.39    5481 1430.36
  5537.2 1432.84  5574.7 1433.66  5601.6 1435.39  5730.4 1437.39  5751.8    1437
#Mann= 8 ,-1 , 0
  4573.3     .12       0  4590.1     .05       0  4803.3     .12       0
  4985.1     .05       0  4994.2     .03       0  4999.2     .05       0
  5405.6     .12       0    5481     .05       0
Bank Sta=4994.2,4999.2
XS Rating Curve= 0 ,0
Exp/Cntr=0.3,0.1

Type RM Length L Ch R = 1 ,7500    ,500,500,500
BEGIN DESCRIPTION:
SANFERNANDO013 15.0
END DESCRIPTION:
XS GIS Cut Line= 3
      2743005.68     10289303.11      2742881.73     10289071.71
      2742705.68      10288703.1
#Sta/Elev= 30
  4737.5 1427.36  4795.2 1423.09  4811.4 1421.37  4833.4 1421.23  4849.6 1418.36
  4855.3 1418.77  4862.3 1417.74  4893.5 1417.62  4935.7 1412.28    4953 1410.93
  4987.1 1404.53    5000 1403.51  5006.9 1401.74  5007.3 1401.24  5011.7 1401.24
  5012.1 1401.74  5042.8 1405.32  5054.1 1407.65  5079.1 1409.94  5099.5 1411.47
  5122.2 1412.25  5212.9 1414.58    5230 1414.12  5235.6 1414.83  5252.7 1415.16
  5264.4 1416.95  5275.4 1417.42  5286.6 1418.92  5326.3 1420.72  5408.5 1426.06
#Mann= 5 ,-1 , 0
  4737.5     .05       0  4935.7     .12       0  5006.9     .07       0
  5012.1     .12       0  5079.1     .05       0
Bank Sta=5006.9,5012.1
XS Rating Curve= 0 ,0
Exp/Cntr=0.3,0.1

Type RM Length L Ch R = 1 ,7000    ,500,500,500
BEGIN DESCRIPTION:
SANFERNANDO013 14.0
END DESCRIPTION:
XS GIS Cut Line= 3
      2743605.71     10288953.12      2743087.22     10288625.72
      2742605.67     10288553.11
#Sta/Elev= 30
  4386.8 1417.98  4525.1 1412.71  4699.5 1408.68  4728.6 1408.45  4749.8 1405.62
  4755.7 1407.06  4765.1 1405.59    4771 1406.44  4786.3 1403.82  4792.2 1404.85
  4807.5 1402.54  4813.4 1403.54  4822.7 1402.16  4828.6 1403.63  4880.4 1400.26
  4922.8 1399.98  4938.1 1402.03  4966.3 1401.35    4995  1397.4  4995.5  1396.9
    5001  1397.4  5072.3 1399.54    5118 1404.22  5186.9 1407.31  5250.8 1413.79
  5319.7 1418.41  5383.6 1427.09  5388.6 1426.18  5400.7 1427.84    5487 1431.57
#Mann= 5 ,-1 , 0
  4386.8     .12       0  4699.5     .05       0    4995     .03       0
    5001     .05       0  5400.7     .12       0
Bank Sta=4995,5001
XS Rating Curve= 0 ,0
Exp/Cntr=0.3,0.1

Type RM Length L Ch R = 1 ,6500    ,500,500,500
BEGIN DESCRIPTION:
SANFERNANDO013 13.0
END DESCRIPTION:
XS GIS Cut Line= 3
      2744005.65      10288353.1      2743042.25      10288133.1
      2742474.25     10288131.03
#Sta/Elev= 30
  4011.8 1427.02  4035.8 1425.88  4052.8 1423.62  4073.3 1419.89  4078.8 1417.81
  4114.3 1411.99  4164.7 1408.02  4303.9 1402.42  4329.7 1400.55  4346.9 1397.21
  4372.8  1396.7  4411.8 1399.19  4480.9 1399.97  4660.3 1398.76  4832.4 1400.37
  4911.6 1396.64  4936.3 1395.91  4955.4 1393.27  4974.2 1392.46  4992.7 1388.86
  4993.2 1388.36  4998.7 1388.86  5026.6 1394.02  5110.5 1398.11  5156.6 1399.29
  5226.6 1398.59  5406.8 1405.39  5526.6 1410.35  5551.2 1413.94    5568 1414.98
#Mann= 9 ,-1 , 0
  4011.8     .12       0  4372.8     .05       0  4660.3     .12       0
  4911.6     .05       0  4992.7     .05       0  4998.7     .05       0
  5110.5     .12       0  5406.8     .05       0  5551.2     .12       0
Bank Sta=4992.7,4998.7
XS Rating Curve= 0 ,0
Exp/Cntr=0.3,0.1