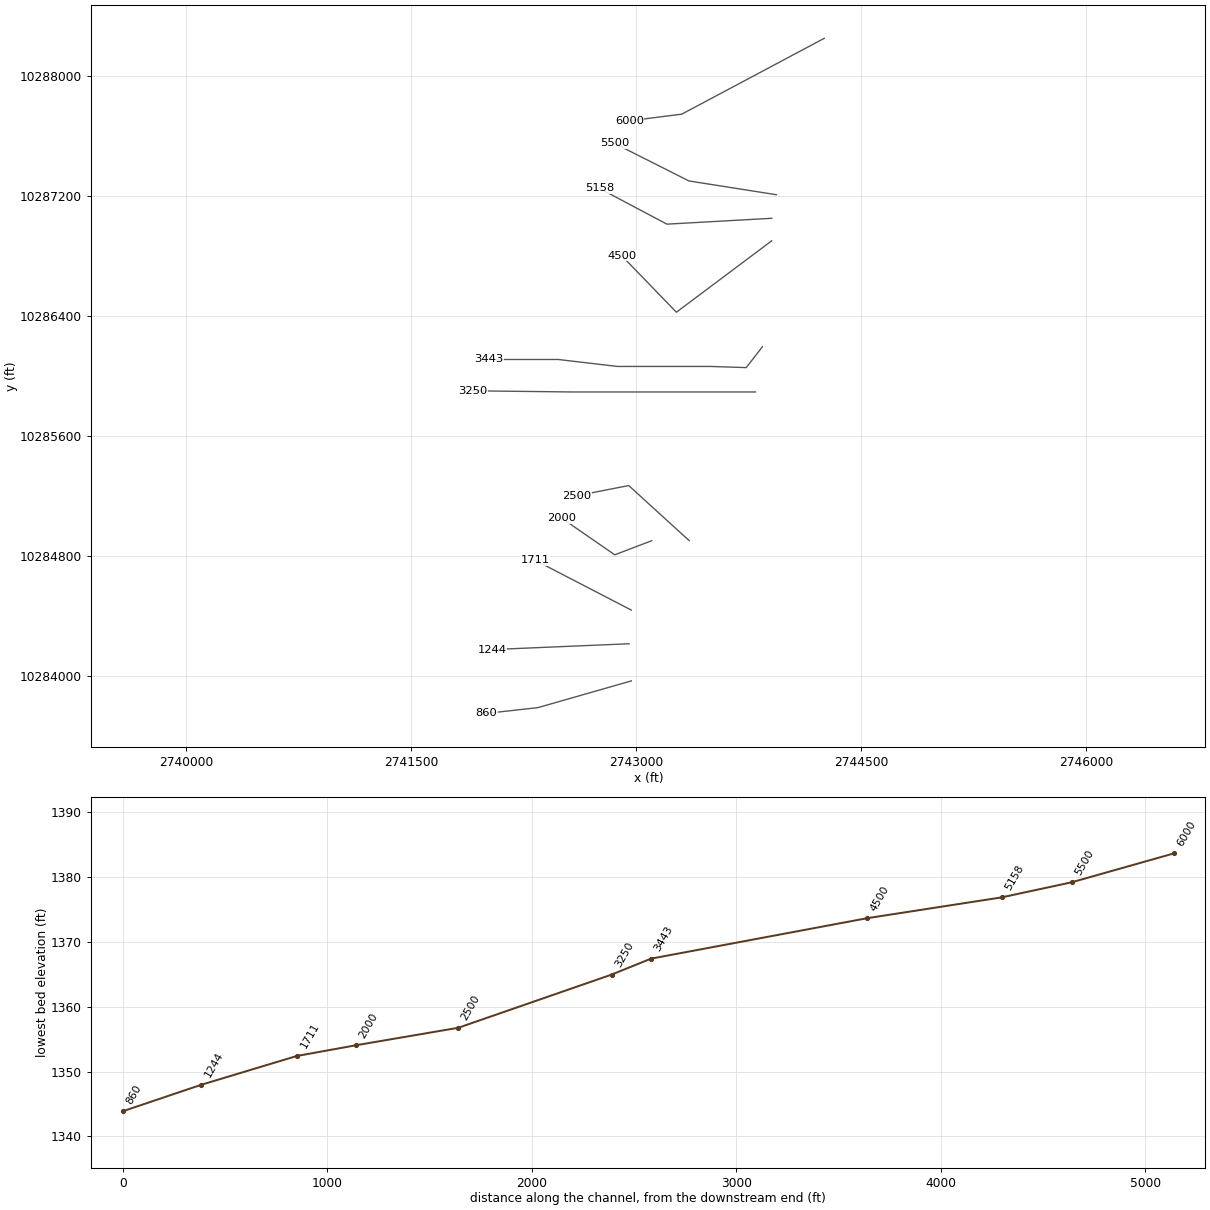
HEC-RAS study SANFERNANDO013.prj: SANFERNANDO013 Base Level Engineering

--- SANFERNANDO013.g01 (geometry) --- (continued)

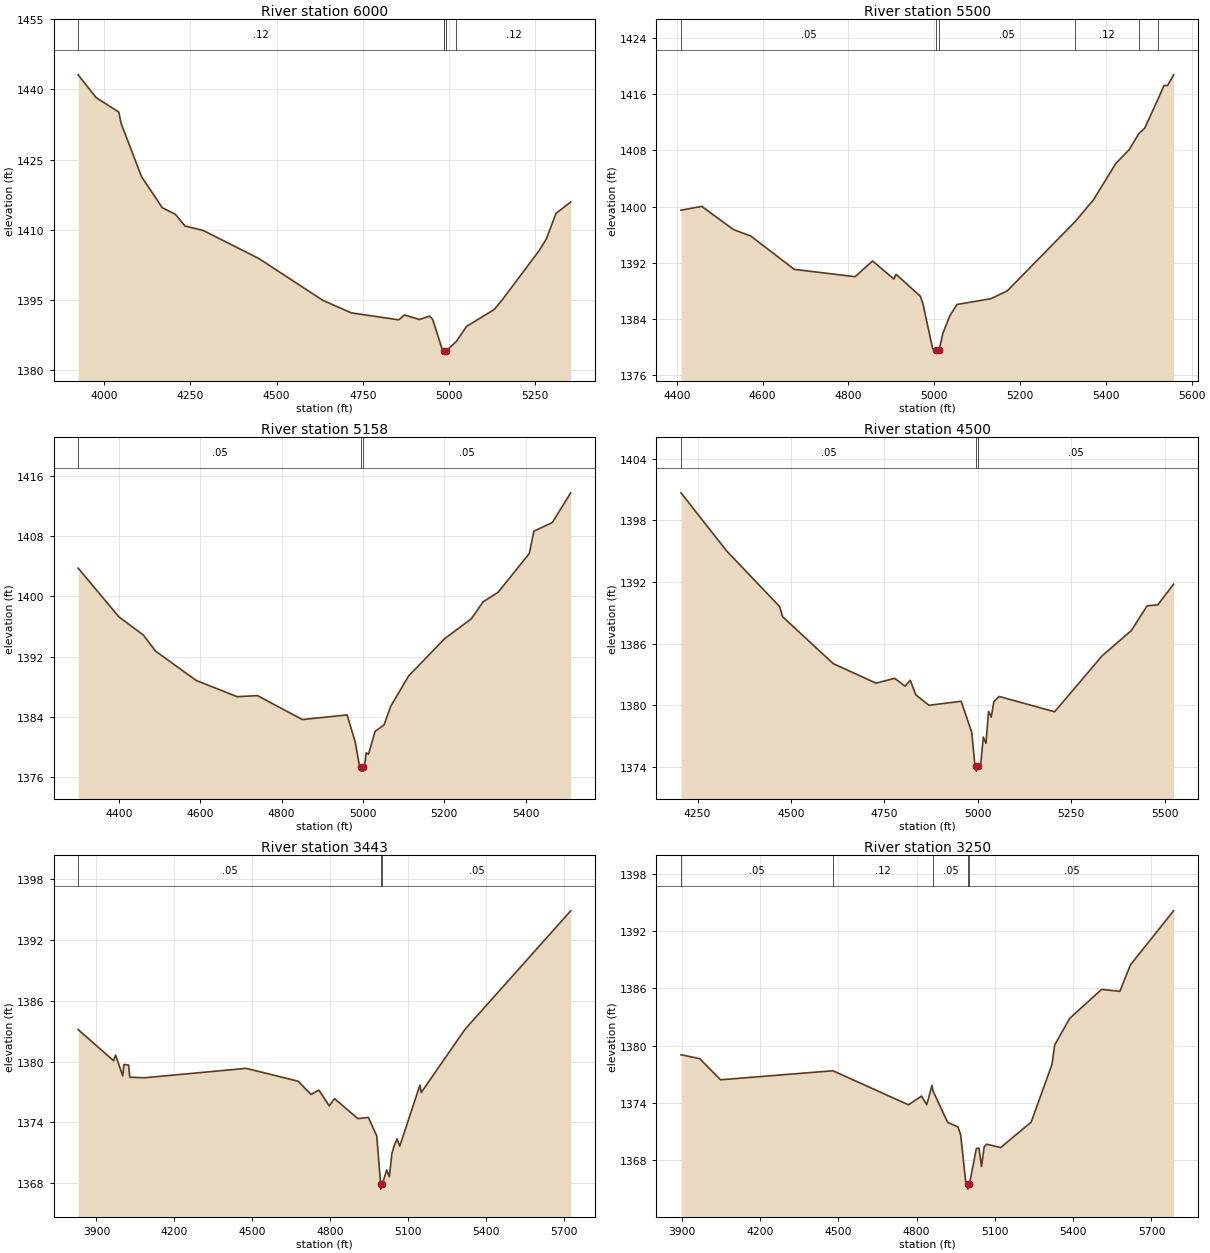
Type RM Length L Ch R = 1 ,6000    ,500,500,500
BEGIN DESCRIPTION:
SANFERNANDO013 12.0
END DESCRIPTION:
XS GIS Cut Line= 3
      2744255.69     10288253.11      2743305.96     10287747.57
      2742955.67     10287703.11
#Sta/Elev= 30
  3924.1 1443.12  3976.2 1438.25  4042.1 1435.15  4048.7 1432.72    4108 1421.33
  4168.3 1414.69  4206.5 1413.28  4234.2 1410.78  4286.6 1409.84  4448.2 1403.84
  4634.6 1394.86  4716.8 1392.21  4854.3 1390.72  4870.6 1391.76  4914.5 1390.79
  4943.7 1391.53  4952.8 1390.79  4980.4 1384.39  4985.6 1384.12  4985.9  1384.1
  4986.4  1383.6    4992  1384.1  5021.3  1386.1  5050.7  1389.3  5131.3 1392.94
  5155.5  1395.1  5262.4 1405.61  5282.5 1408.03  5310.6  1413.5  5353.1 1415.91
#Mann= 5 ,-1 , 0
  3924.1     .12       0  4985.6     .05       0  4985.9     .05       0
    4992     .05       0  5021.3     .12       0
Bank Sta=4985.9,4992
XS Rating Curve= 0 ,0
Exp/Cntr=0.3,0.1

Type RM Length L Ch R = 1 ,5500    ,342,342,342
BEGIN DESCRIPTION:
SANFERNANDO013 11.0
END DESCRIPTION:
XS GIS Cut Line= 3
       2743936.6      10287210.3      2743353.77     10287302.06
      2742855.67     10287553.12
#Sta/Elev= 30
    4410 1399.48  4458.3 1400.02  4532.4 1396.72  4572.9 1395.79  4674.1 1391.06
  4815.8 1390.02  4856.3 1392.26  4906.1 1389.69  4911.2 1390.36  4967.7 1387.24
  4973.7  1386.2  4996.5 1379.77  5005.3 1379.65  5005.8 1379.15  5011.7 1379.65
  5020.3 1381.98  5036.4 1384.46  5053.1 1386.07  5132.2 1386.89  5170.2    1388
  5328.7 1397.87    5371 1400.94  5423.4 1406.14  5454.6  1408.1  5476.7 1410.36
  5490.6 1411.14  5522.5  1415.4  5535.4 1417.21  5543.8 1417.21  5557.8 1418.73
#Mann= 6 ,-1 , 0
    4410     .05       0  5005.3     .03       0  5011.7     .05       0
  5328.7     .12       0  5476.7     .05       0  5522.5     .12       0
Bank Sta=5005.3,5011.7
XS Rating Curve= 0 ,0
Exp/Cntr=0.3,0.1

Type RM Length L Ch R = 1 ,5158    ,658,658,658
BEGIN DESCRIPTION:
SANFERNANDO013 10.0
END DESCRIPTION:
XS GIS Cut Line= 3
      2743905.66     10287053.11      2743206.75       10287014.
      2742755.71      10287253.1
#Sta/Elev= 30
    4300 1403.74  4400.1 1397.28  4460.2 1394.87  4490.3 1392.73  4590.4 1388.84
  4690.6  1386.7  4740.7 1386.84  4850.8 1383.67    4961 1384.28    4981 1380.67
  4991.1 1377.58  4994.8 1377.33  4995.3 1376.83  5000.7 1376.83  5001.2 1377.33
  5003.4 1377.33  5007.8 1379.26  5013.5 1379.07  5029.8 1382.11  5051.8 1382.95
  5068.1 1385.42  5112.1 1389.44  5200.1 1394.36  5266.1 1397.02  5295.5 1399.28
  5332.1 1400.54  5408.7 1405.67    5420 1408.64  5465.3 1409.78  5510.5 1413.72
#Mann= 3 ,-1 , 0
    4300     .05       0  4994.8     .05       0  5001.2     .05       0
Bank Sta=4994.8,5001.2
XS Rating Curve= 0 ,0
Exp/Cntr=0.3,0.1

Type RM Length L Ch R = 1 ,4500    ,1057,1057,1057
BEGIN DESCRIPTION:
SANFERNANDO013 9.0
END DESCRIPTION:
XS GIS Cut Line= 3
      2743905.67      10286903.1       2743269.9      10286426.8
      2742905.69     10286803.11
#Sta/Elev= 30
  4205.6 1400.67  4327.5 1395.03  4469.2 1389.63  4477.5 1388.63  4612.9 1384.07
  4727.5 1382.17  4777.5 1382.64  4805.3 1381.88  4819.2 1382.45  4833.8 1381.04
  4869.2 1380.02  4955.3 1380.41  4983.8 1377.37  4992.2 1374.14  4995.2 1374.12
  4995.7 1373.62  5001.7 1374.12  5007.5 1374.23  5014.5 1376.93  5021.7 1376.32
  5028.6 1379.43  5035.8 1378.87  5042.8 1380.38  5056.9 1380.88  5205.4 1379.39
  5332.7 1384.83  5410.6 1387.28  5453.1 1389.69  5481.4 1389.78  5523.7 1391.79
#Mann= 3 ,-1 , 0
  4205.6     .05       0  4995.2     .05       0  5001.7     .05       0
Bank Sta=4995.2,5001.7
XS Rating Curve= 0 ,0
Exp/Cntr=0.3,0.1

Type RM Length L Ch R = 1 ,3443    ,193,193,193
BEGIN DESCRIPTION:
Mapping XS 5bb801c8
END DESCRIPTION:
XS GIS Cut Line= 6
      2743843.71      10286196.7      2743735.42     10286057.46
      2743495.56      10286065.2      2742876.59      10286065.2
      2742481.99     10286111.62      2742019.26     10286111.62
#Sta/Elev= 30
  3829.5 1383.16  3965.9 1380.08  3973.4 1380.65  4001.2 1378.58  4005.5 1379.71
  4023.3 1379.66  4028.3 1378.45  4085.7  1378.4  4475.8 1379.33  4675.8 1378.06
  4725.8 1376.75  4755.8 1377.18  4795.8 1375.62  4815.8 1376.34    4906 1374.36
  4946.3 1374.48  4978.5 1372.65  4993.4 1367.89  4993.9 1367.39    5000 1367.89
  5016.8 1369.28  5026.9 1368.61  5036.9 1370.93    5047 1371.76  5056.5 1372.36
  5067.1 1371.63  5144.6 1377.67  5149.6 1376.94  5318.5  1383.2  5724.9  1394.9
#Mann= 3 ,-1 , 0
  3829.5     .05       0  4993.4     .03       0    5000     .05       0
Bank Sta=4993.4,5000
XS Rating Curve= 0 ,0
Exp/Cntr=0.3,0.1

Type RM Length L Ch R = 1 ,3250    ,750,750,750
BEGIN DESCRIPTION:
Mapping XS b1082888
END DESCRIPTION:
XS GIS Cut Line= 4
      2743797.31     10285894.98      2743147.39     10285894.98
      2742574.84     10285894.98      2741910.05     10285902.71
#Sta/Elev= 30
  3897.3 1379.04  3968.9 1378.63  4048.9 1376.41  4479.2 1377.36  4768.9 1373.78
  4818.9  1374.7  4838.9 1373.79  4858.9 1375.82  4862.8 1375.25  4918.9 1371.94
  4958.9 1371.46  4968.9 1370.62  4988.9 1365.52  4995.6 1365.43  4996.1 1364.93
  5002.3 1365.43  5028.9 1369.18  5038.9 1369.24  5048.9 1367.31  5058.9 1369.37
  5068.9 1369.65  5121.8 1369.29  5238.9 1371.96  5318.9 1378.03  5328.9 1380.05
  5386.4 1382.85  5508.9  1385.9    5579  1385.7    5619 1388.46  5784.6 1394.15
#Mann= 5 ,-1 , 0
  3897.3     .05       0  4479.2     .12       0  4862.8     .05       0
  4995.6     .05       0  5002.3     .05       0
Bank Sta=4995.6,5002.3
XS Rating Curve= 0 ,0
Exp/Cntr=0.3,0.1

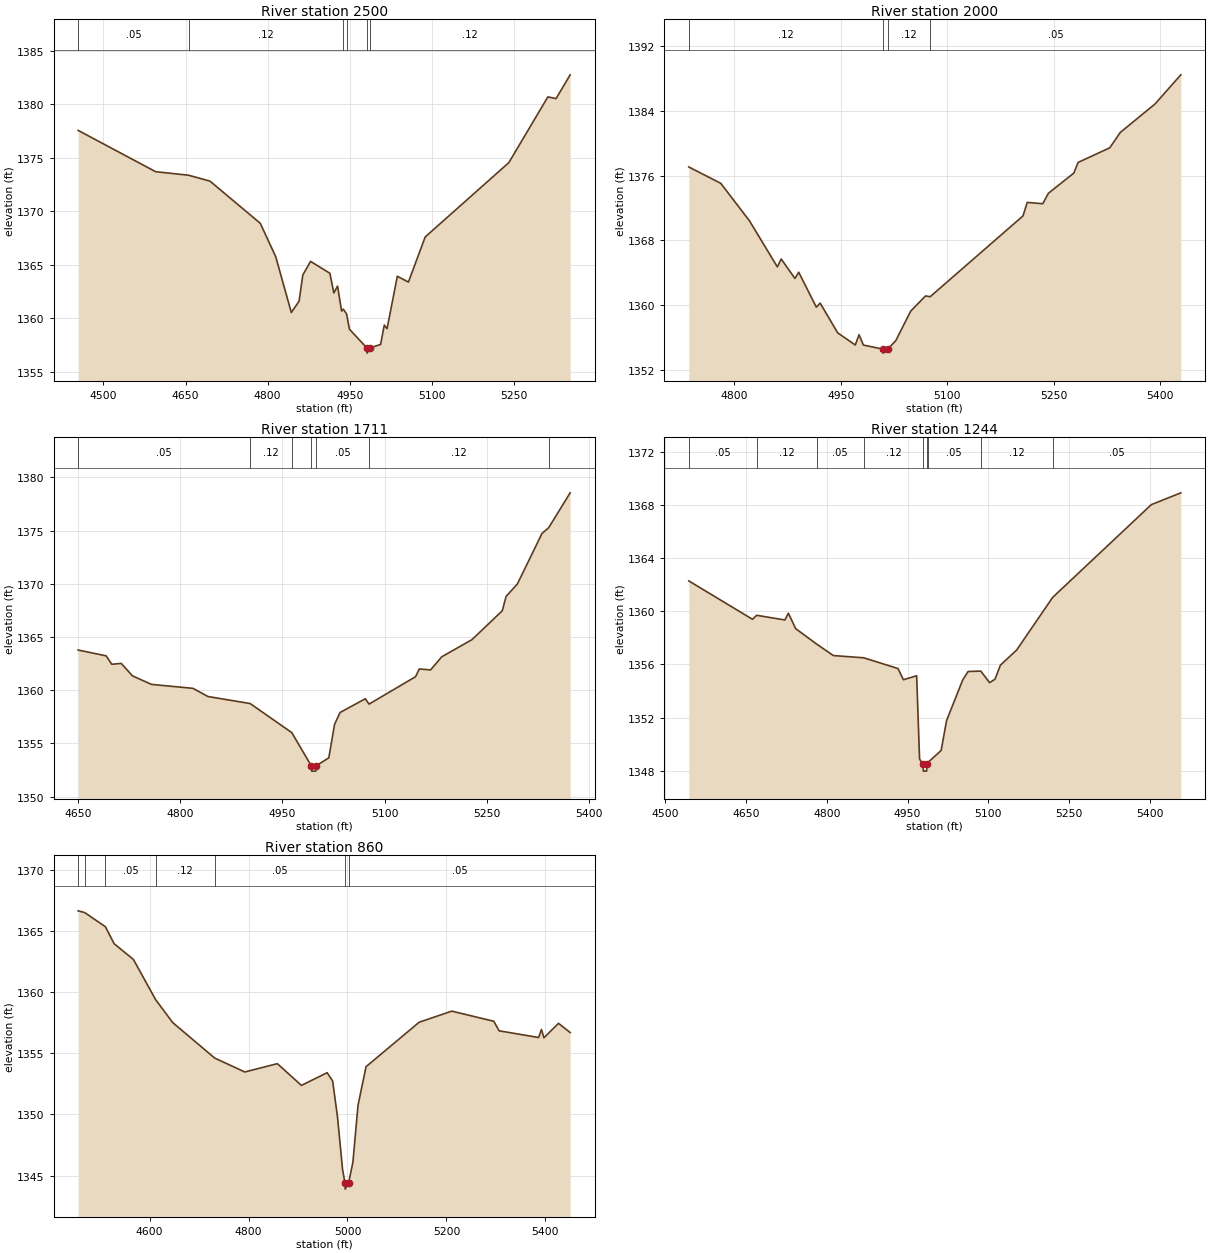
Type RM Length L Ch R = 1 ,2500    ,500,500,500
BEGIN DESCRIPTION:
SANFERNANDO013 5.0
END DESCRIPTION:
XS GIS Cut Line= 3
      2743355.69      10284903.1      2742951.95     10285270.97
      2742605.73     10285203.12
#Sta/Elev= 30
  4453.8 1377.55  4595.4 1373.69  4655.7 1373.36  4694.7 1372.81  4786.6 1368.87
  4814.9 1365.74  4843.3 1360.54  4857.5 1361.59  4864.3 1364.04  4878.5 1365.31
  4913.8  1364.2    4921 1362.36  4927.8    1363  4935.2 1360.67  4938.3 1360.85
  4944.4 1360.39  4949.4 1358.98  4981.1 1357.24  4981.6 1356.74  4987.9 1357.24
  5006.4 1357.55  5013.2 1359.36  5018.3 1359.03    5037 1363.92  5057.3 1363.38
  5087.9 1367.59  5240.8 1374.54  5312.1 1380.68  5327.1 1380.52  5352.8 1382.74
#Mann= 6 ,-1 , 0
  4453.8     .05       0  4655.7     .12       0  4938.3     .05       0
  4944.4     .12       0  4981.1     .07       0  4987.9     .12       0
Bank Sta=4981.1,4987.9
XS Rating Curve= 0 ,0
Exp/Cntr=0.3,0.1

Type RM Length L Ch R = 1 ,2000    ,289,289,289
BEGIN DESCRIPTION:
SANFERNANDO013 4.0
END DESCRIPTION:
XS GIS Cut Line= 3
      2743105.65      10284903.1      2742858.69     10284809.23
      2742505.65     10285053.14
#Sta/Elev= 30
  4735.8 1377.09  4780.9 1375.06  4821.4 1370.41  4860.6 1364.72    4866  1365.7
  4885.4 1363.29  4890.7 1364.06  4915.5 1359.74  4920.9 1360.24  4945.6 1356.56
  4970.4 1355.06  4975.7 1356.33  4981.8 1355.05  5009.1 1354.55  5009.6 1354.05
  5016.2 1354.55  5027.5  1355.6  5048.5 1359.25  5069.4 1361.13  5075.9 1361.03
  5206.7 1371.03  5212.7  1372.7  5234.6 1372.54  5242.5 1373.83  5278.3 1376.33
  5284.4 1377.65    5329 1379.46  5343.9 1381.37  5392.6 1384.87  5429.1 1388.49
#Mann= 4 ,-1 , 0
  4735.8     .12       0  5009.1     .07       0  5016.2     .12       0
  5075.9     .05       0
Bank Sta=5009.1,5016.2
XS Rating Curve= 0 ,0
Exp/Cntr=0.3,0.1

Type RM Length L Ch R = 1 ,1711    ,467,467,467
BEGIN DESCRIPTION:
Mapping XS ff850959
END DESCRIPTION:
XS GIS Cut Line= 2
      2742969.45     10284440.38        2742329.     10284772.18
#Sta/Elev= 30
  4650.5 1363.78  4691.6 1363.23  4699.8 1362.44  4713.7 1362.52  4730.2 1361.35
    4758 1360.55  4818.8 1360.18  4840.9 1359.41  4902.7 1358.75  4963.7 1356.02
  4992.3  1352.9  4992.8  1352.4  4998.9  1352.4  4999.4  1352.9    5018 1353.65
  5026.4 1356.79  5034.5 1357.91  5071.5  1359.2    5077  1358.7  5145.1 1361.27
  5150.7    1362  5167.2 1361.91  5183.7 1363.15    5228 1364.76  5272.3 1367.47
  5277.9 1368.82  5294.4 1369.98  5330.5 1374.73  5340.3 1375.27  5371.8 1378.55
#Mann= 7 ,-1 , 0
  4650.5     .05       0  4902.7     .12       0  4963.7     .05       0
  4992.3     .05       0  4999.4     .05       0    5077     .12       0
  5340.3     .05       0
Bank Sta=4992.3,4999.4
XS Rating Curve= 0 ,0
Exp/Cntr=0.3,0.1

Type RM Length L Ch R = 1 ,1244    ,384,384,384
BEGIN DESCRIPTION:
Mapping XS cd2f311b
END DESCRIPTION:
XS GIS Cut Line= 2
      2742953.92     10284216.01      2742040.94     10284177.32
#Sta/Elev= 30
  4543.7 1362.29    4662  1359.4  4669.7  1359.7  4722.1 1359.35  4728.7 1359.86
  4742.1  1358.7  4781.3 1357.53  4812.2 1356.67  4868.8  1356.5  4932.3 1355.69
  4942.3 1354.85  4966.9 1355.15  4972.3 1348.88  4978.8 1348.47  4979.3 1347.97
  4985.4 1347.97  4985.9 1348.47  4987.3  1348.6  5012.4 1349.53  5022.4 1351.77
  5052.4 1354.83  5062.4 1355.47    5086  1355.5  5102.4 1354.63  5112.4 1354.89
  5122.5 1355.95  5152.5 1357.08  5219.5 1361.05  5402.7 1368.03  5457.5 1368.92
#Mann= 9 ,-1 , 0
  4543.7     .05       0  4669.7     .12       0  4781.3     .05       0
  4868.8     .12       0  4978.8     .05       0  4985.9     .12       0
  4987.3     .05       0    5086     .12       0  5219.5     .05       0
Bank Sta=4978.8,4985.9
XS Rating Curve= 0 ,0
Exp/Cntr=0.3,0.1

Type RM Length L Ch R = 1 ,860     ,0,0,0
BEGIN DESCRIPTION:
SANFERNANDO013 2.0
END DESCRIPTION:
XS GIS Cut Line= 3
      2742969.47     10283968.43      2742346.03     10283789.94
      2742002.33     10283751.78
#Sta/Elev= 30
  4455.7 1366.67  4468.8 1366.53  4510.8 1365.37  4528.4 1363.98  4567.4 1362.69
  4612.3  1359.4  4646.9 1357.52  4731.6 1354.62  4792.5 1353.48  4858.3 1354.16
  4906.9 1352.38  4958.9 1353.42    4970 1352.74  4979.7 1349.85  4990.1 1345.49
    4995 1344.39  4995.5 1343.89  5002.2 1344.39  5010.9 1346.07  5021.3 1350.75
  5037.5 1353.91  5144.8 1357.55  5210.8 1358.46  5295.7 1357.63  5306.4 1356.85
  5386.3  1356.3    5392 1356.96    5397 1356.28  5426.5 1357.46    5450 1356.71
#Mann= 7 ,-1 , 0
  4455.7     .05       0  4468.8     .12       0  4510.8     .05       0
  4612.3     .12       0  4731.6     .05       0    4995     .05       0
  5002.2     .05       0
Bank Sta=4995,5002.2
XS Rating Curve= 0 ,0
Exp/Cntr=0.3,0.1
Stream Node=SANFERNANDO013  ,Reach-1         , 0 , 0 ,Upstream end
Stream Node=SANFERNANDO013  ,Reach-1         , 0 , 1 ,Downstream end

Chan Stop Cuts=-1
Use User Specified Reach Order=0
Composite Channel Slope=5