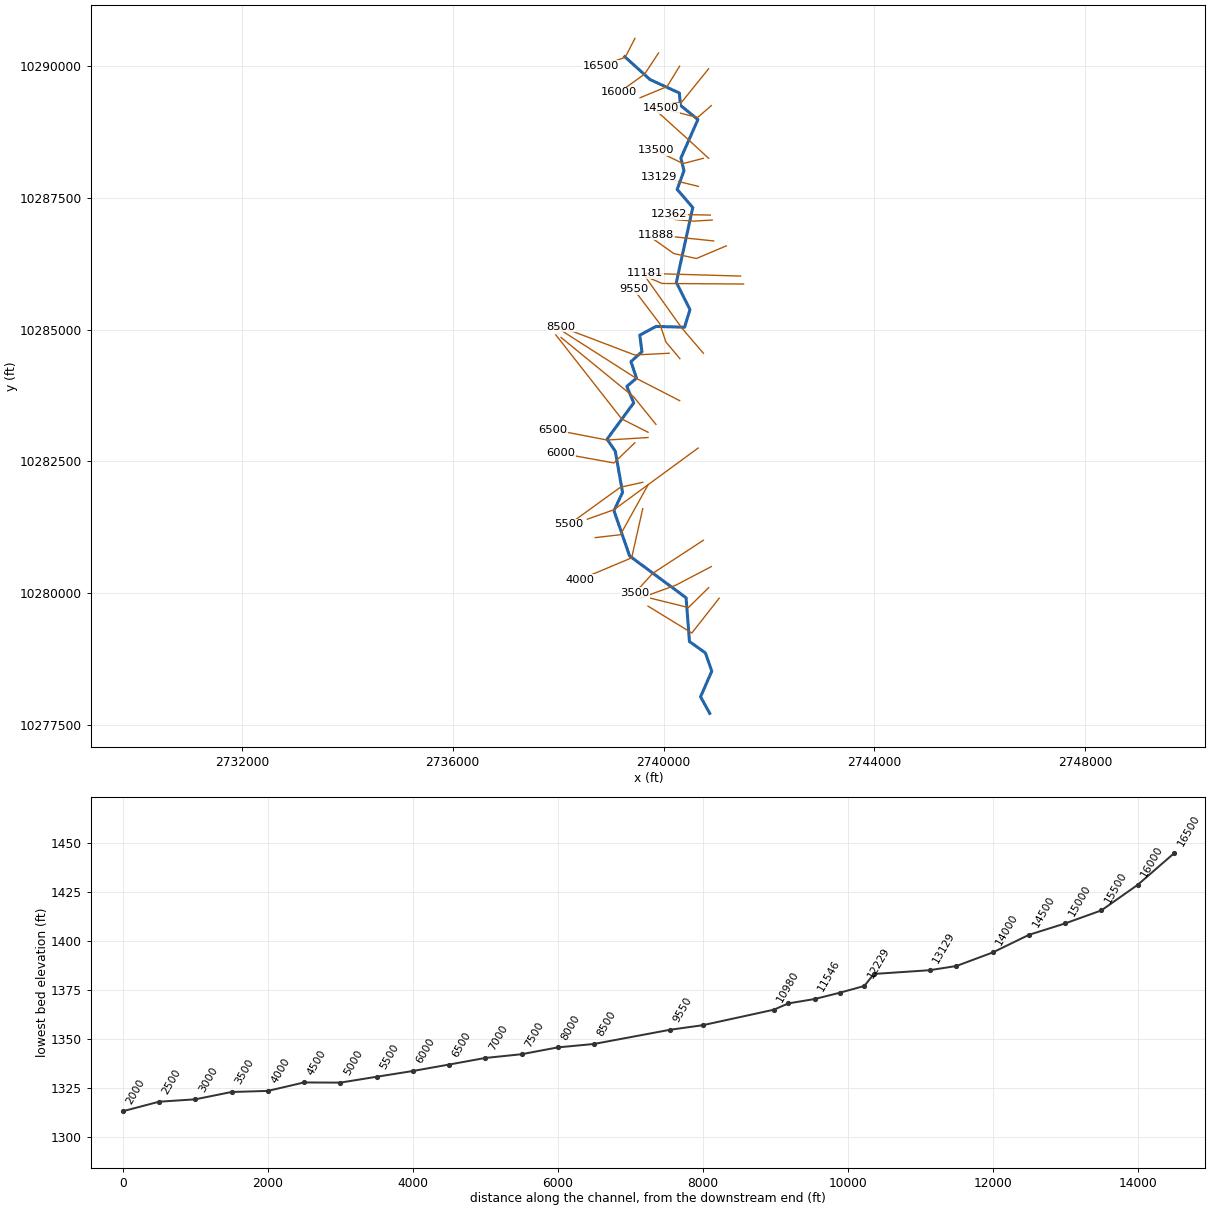
--- SANFERNANDO015.prj (project) ---

Proj Title=SANFERNANDO015 Base Level Engineering
Current Plan=p01
Default Exp/Contr=0.3,0.1
English Units
Geom File=g01
Flow File=f01
Plan File=p01
BEGIN DESCRIPTION:
SANFERNANDO015
END DESCRIPTION:

--- SANFERNANDO015.p01 (plan) ---

Plan Title=Multiple Run
Short Identifier=Multiple
Geom File=g01
Flow File=f01
Subcritical Flow
K Sum by GR= 0
Std Step Tol= 0.01
Critical Tol= 0.01
Num of Std Step Trials= 20
Max Error Tol= 0.3
Flow Tol Ratio= 0.001
Split Flow NTrial= 30
Split Flow Tol= 0.02
Split Flow Ratio= 0.02
Log Output Level= 0
Friction Slope Method= 1
Unsteady Friction Slope Method= 2
Unsteady Bridges Friction Slope Method= 1
Parabolic Critical Depth
Global Vel Dist=  1 , 1 , 1
Global Log Level= 0
CheckData=True
Encroach Param= -1, 0, 0, 0
BEGIN DESCRIPTION:
Multiple Run
END DESCRIPTION:

--- SANFERNANDO015.f01 (steady flow) ---

Flow Title=Multiple
Number of Profiles=7
Profile Names=10-year,25-year,50-year,1pct_min,100-year,1pct_plu,500-year
River Rch & RM= SANFERNANDO015,Reach-1,16500
     503     824    1087     922    1455    2297    2000
River Rch & RM= SANFERNANDO015,Reach-1,5000
     694    1166    1491    1052    2012    3847    2757
Boundary for River Rch & Prof#=SANFERNANDO015,Reach-1,1
Up Type=0
Dn Type=3
Dn Slope=0.005
Boundary for River Rch & Prof#=SANFERNANDO015,Reach-1,2
Up Type=0
Dn Type=3
Dn Slope=0.005
Boundary for River Rch & Prof#=SANFERNANDO015,Reach-1,3
Up Type=0
Dn Type=3
Dn Slope=0.005
Boundary for River Rch & Prof#=SANFERNANDO015,Reach-1,4
Up Type=0
Dn Type=3
Dn Slope=0.005
Boundary for River Rch & Prof#=SANFERNANDO015,Reach-1,5
Up Type=0
Dn Type=3
Dn Slope=0.005
Boundary for River Rch & Prof#=SANFERNANDO015,Reach-1,6
Up Type=0
Dn Type=3
Dn Slope=0.005
Boundary for River Rch & Prof#=SANFERNANDO015,Reach-1,7
Up Type=0
Dn Type=3
Dn Slope=0.005

--- SANFERNANDO015.g01 (geometry) ---

Geom Title=Existing Conditions

River Reach=SANFERNANDO015,Reach-1
Reach XY= 30
      2739264.50     10290182.00      2739744.00     10289748.00
      2740299.50     10289493.00      2740320.50     10289259.00
      2740652.00     10288989.00      2740329.00     10288257.00
      2740388.00     10288018.00      2740258.50     10287662.00
      2740554.75     10287319.00      2740242.50     10285897.00
      2740501.00     10285382.00      2740399.25     10285047.00
      2739857.00     10285062.00      2739548.75     10284896.00
      2739591.25     10284583.00      2739381.75     10284393.00
      2739488.00     10284080.00      2739303.75     10283924.00
      2739435.00     10283611.00      2738928.75     10282921.00
      2739085.00     10282693.00      2739222.50     10281911.00
      2739060.00     10281564.00      2739356.50     10280705.00
      2740428.00     10279911.00      2740491.50     10279081.00
      2740794.75     10278864.00      2740915.25     10278518.00
      2740702.75     10278033.00      2740876.25     10277717.00

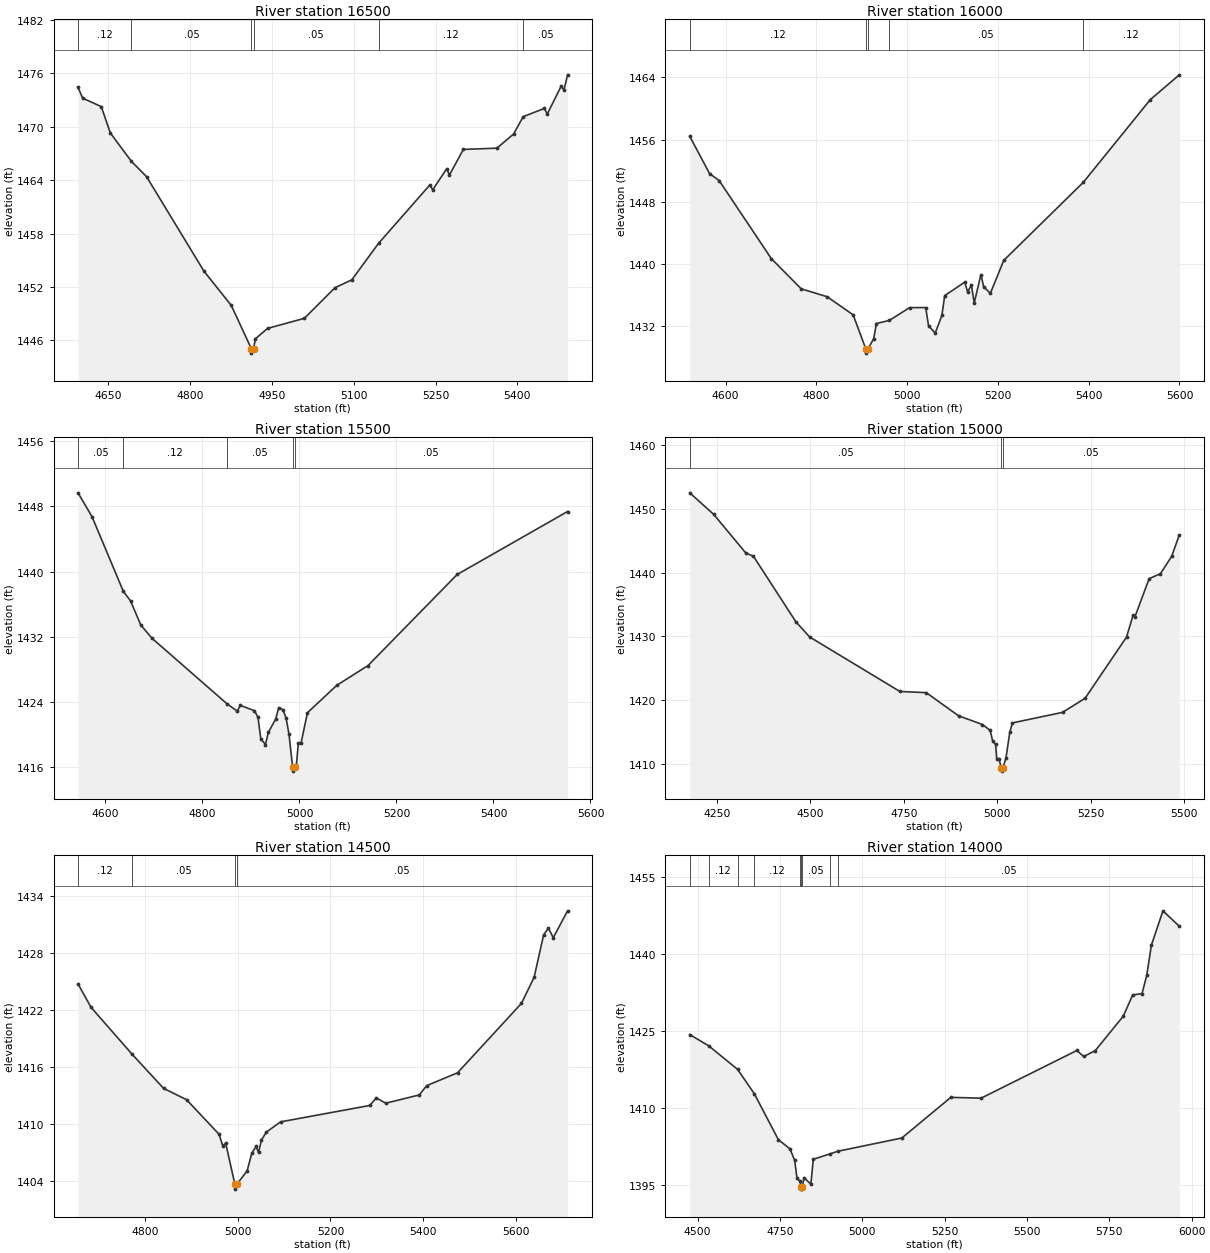
Type RM Length L Ch R = 1,16500,500,500,500
BEGIN DESCRIPTION:
SANFERNANDO015 32.0
END DESCRIPTION:
XS GIS Cut Line= 3
      2739457.83     10290530.63      2739272.31     10290170.39
      2738809.23     10290004.21
#Sta/Elev= 30
  4594.8 1474.43  4603.3 1473.22  4637.4 1472.27  4654.0 1469.31  4692.6 1466.12
  4720.5 1464.39  4825.7 1453.77  4875.7 1449.93  4912.4 1445.07  4912.6 1444.57
  4916.4 1445.07  4920.0 1446.19  4942.2 1447.35  5009.6 1448.48  5065.7 1451.92
  5096.5 1452.80  5145.5 1456.90  5239.5 1463.46  5244.8 1462.92  5270.3 1465.27
  5275.6 1464.60  5301.0 1467.46  5362.5 1467.60  5393.2 1469.20  5410.6 1471.14
  5449.4 1472.06  5454.7 1471.43  5480.1 1474.55  5485.4 1474.15  5492.0 1475.84
#Mann=6,-1,0
  4594.8    0.12       0  4692.6    0.05       0  4912.4    0.05       0
  4916.4    0.05       0  5145.5    0.12       0  5410.6    0.05       0
Bank Sta=4912.4,4916.4
Exp/Cntr=0.3,0.1

Type RM Length L Ch R = 1,16000,500,500,500
BEGIN DESCRIPTION:
SANFERNANDO015 31.0
END DESCRIPTION:
XS GIS Cut Line= 3
      2739905.68     10290253.11      2739642.52     10289853.12
      2739155.68     10289503.11
#Sta/Elev= 30
  4521.2 1456.42  4564.9 1451.62  4586.0 1450.73  4700.8 1440.70  4766.7 1436.81
  4823.9 1435.79  4881.1 1433.46  4909.3 1429.04  4909.6 1428.54  4913.3 1429.04
  4926.4 1430.40  4932.4 1432.35  4960.6 1432.74  5005.4 1434.39  5041.0 1434.40
  5047.2 1432.05  5061.9 1431.12  5076.6 1433.39  5082.8 1435.94  5127.0 1437.67
  5133.1 1436.44  5141.7 1437.26  5147.8 1435.00  5162.6 1438.64  5168.7 1437.07
  5183.4 1436.24  5212.9 1440.47  5388.0 1450.50  5535.7 1461.14  5599.6 1464.33
#Mann=5,-1,0
  4521.2    0.12       0  4909.3    0.05       0  4913.3    0.12       0
  4960.6    0.05       0  5388.0    0.12       0
Bank Sta=4909.3,4913.3
Exp/Cntr=0.3,0.1

Type RM Length L Ch R = 1,15500,500,500,500
BEGIN DESCRIPTION:
SANFERNANDO015 30.0
END DESCRIPTION:
XS GIS Cut Line= 3
      2740305.66     10290003.08      2740066.64     10289614.16
      2739555.71     10289403.12
#Sta/Elev= 30
  4543.5 1449.67  4572.5 1446.73  4636.9 1437.59  4651.7 1436.43  4673.0 1433.46
  4696.0 1431.84  4850.3 1423.82  4872.0 1422.90  4877.8 1423.62  4907.3 1422.96
  4914.5 1422.15  4920.4 1419.49  4930.0 1418.81  4935.8 1420.29  4951.2 1421.96
  4957.1 1423.32  4966.0 1423.08  4972.5 1422.03  4978.4 1420.11  4985.9 1416.05
  4986.2 1415.55  4989.9 1416.05  4993.8 1416.34  4997.7 1418.95  5003.2 1418.95
  5016.5 1422.71  5076.8 1426.06  5141.5 1428.50  5325.2 1439.66  5552.8 1447.38
#Mann=5,-1,0
  4543.5    0.05       0  4636.9    0.12       0  4850.3    0.05       0
  4985.9    0.05       0  4989.9    0.05       0
Bank Sta=4985.9,4989.9
Exp/Cntr=0.3,0.1

Type RM Length L Ch R = 1,15000,500,500,500
BEGIN DESCRIPTION:
SANFERNANDO015 29.0
END DESCRIPTION:
XS GIS Cut Line= 3
      2740855.71     10289953.15      2740338.79     10289313.38
      2739855.64     10289253.11
#Sta/Elev= 30
  4177.5 1452.49  4241.8 1449.10  4327.1 1443.09  4347.9 1442.55  4461.4 1432.29
  4498.1 1429.92  4739.6 1421.38  4810.0 1421.20  4896.3 1417.58  4960.3 1416.21
  4981.1 1415.29  4987.5 1413.63  4995.5 1413.08  4998.5 1410.86  5004.1 1410.86
  5011.2 1409.41  5011.5 1408.91  5015.2 1409.41  5023.3 1410.99  5033.4 1414.97
  5040.5 1416.46  5174.5 1418.11  5234.9 1420.32  5345.8 1429.91  5363.3 1433.34
  5368.3 1433.09  5406.2 1439.05  5436.5 1439.83  5466.7 1442.57  5486.9 1445.91
#Mann=3,-1,0
  4177.5    0.05       0  5011.2    0.05       0  5015.2    0.05       0
Bank Sta=5011.2,5015.2
Exp/Cntr=0.3,0.1

Type RM Length L Ch R = 1,14500,500,500,500
BEGIN DESCRIPTION:
SANFERNANDO015 28.0
END DESCRIPTION:
XS GIS Cut Line= 3
      2740905.66     10289253.09      2740645.16     10289027.35
      2739955.70     10289203.11
#Sta/Elev= 30
  4655.3 1424.75  4683.3 1422.28  4772.1 1417.32  4840.0 1413.72  4889.4 1412.53
  4959.6 1408.88  4967.3 1407.69  4973.9 1407.93  4993.8 1403.59  4994.0 1403.09
  4997.8 1403.59  5020.1 1405.01  5030.4 1406.91  5039.6 1407.59  5044.7 1406.96
  5051.1 1408.27  5061.4 1409.10  5092.3 1410.19  5284.8 1411.92  5298.7 1412.71
  5319.4 1412.16  5391.6 1413.03  5407.5 1414.01  5474.2 1415.37  5611.9 1422.69
  5639.3 1425.44  5659.9 1429.94  5670.2 1430.63  5680.6 1429.62  5711.5 1432.46
#Mann=4,-1,0
  4655.3    0.12       0  4772.1    0.05       0  4993.8    0.05       0
  4997.8    0.05       0
Bank Sta=4993.8,4997.8
Exp/Cntr=0.3,0.1

Type RM Length L Ch R = 1,14000,500,500,500
BEGIN DESCRIPTION:
SANFERNANDO015 27.0
END DESCRIPTION:
XS GIS Cut Line= 3
      2740855.69     10288253.10      2740470.41     10288608.26
      2739755.71     10289253.09
#Sta/Elev= 30
  4476.0 1424.26  4533.9 1422.04  4621.3 1417.47  4672.3 1412.68  4745.1 1403.75
  4780.2 1401.97  4794.4 1399.76  4801.8 1396.20  4810.8 1395.68  4814.0 1394.61
  4814.2 1394.11  4818.0 1394.61  4822.8 1396.35  4843.8 1395.08  4851.1 1399.93
  4901.2 1400.97  4925.8 1401.50  5120.0 1404.08  5268.7 1412.01  5360.7 1411.85
  5651.4 1421.15  5672.3 1419.98  5707.4 1421.13  5792.6 1427.86  5821.0 1431.99
  5849.4 1432.24  5863.6 1435.78  5877.8 1441.69  5912.9 1448.39  5962.6 1445.38
#Mann=9,-1,0
  4476.0    0.05       0  4533.9    0.12       0  4621.3    0.05       0
  4672.3    0.12       0  4810.8    0.05       0  4814.0    0.05       0
  4818.0    0.05       0  4901.2    0.12       0  4925.8    0.05       0
Bank Sta=4814,4818
Exp/Cntr=0.3,0.1

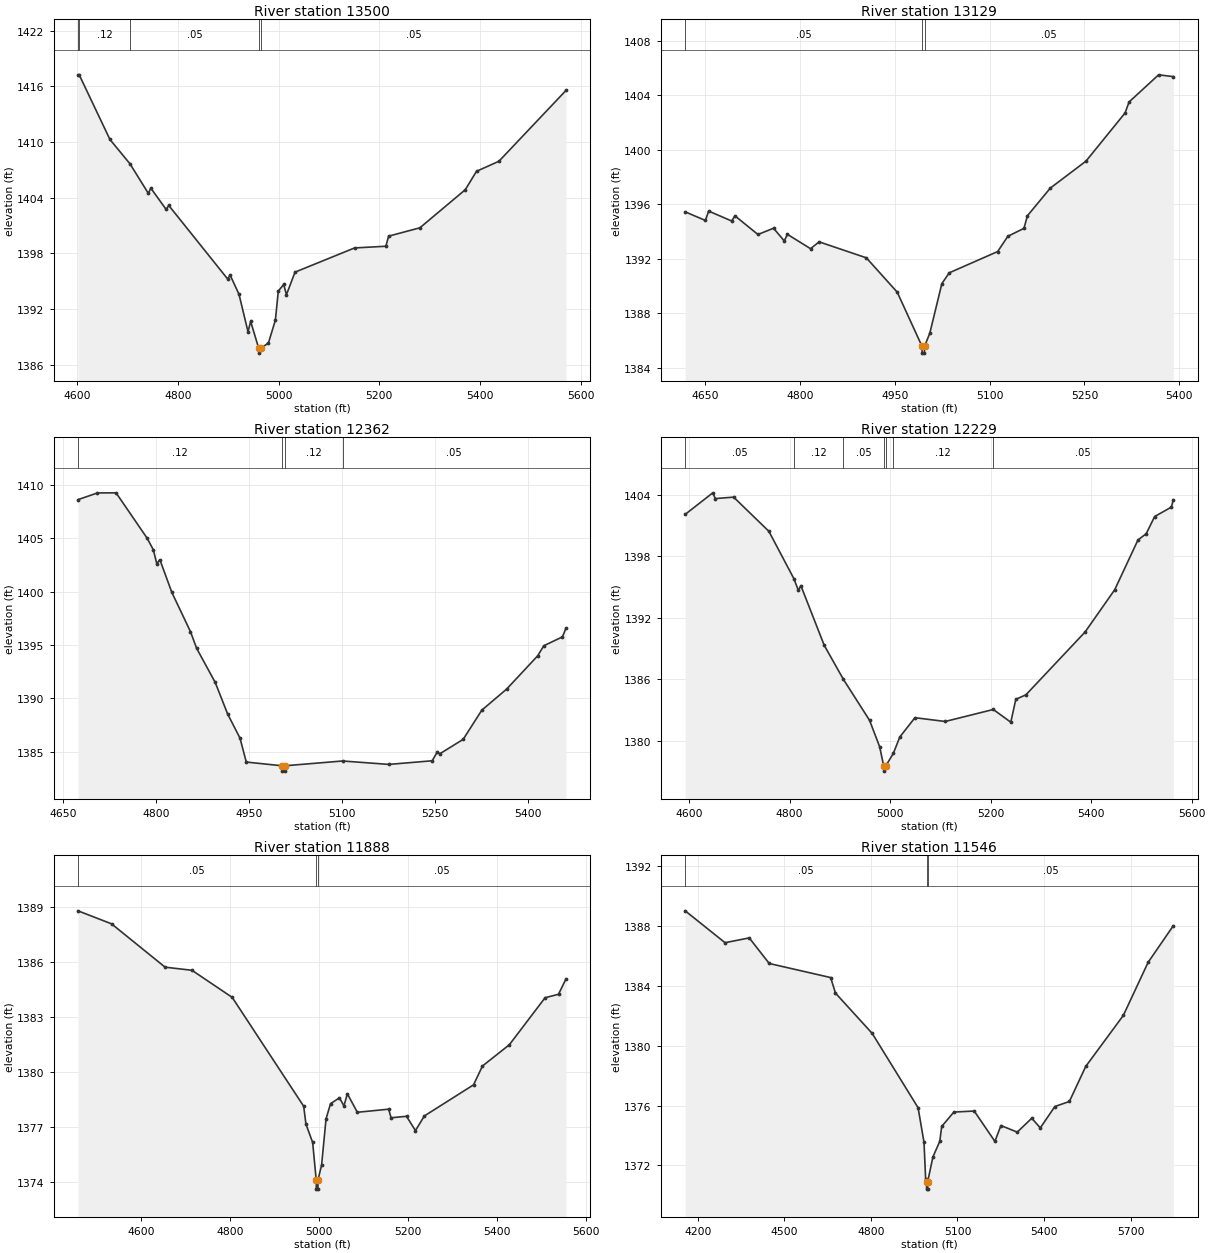
Type RM Length L Ch R = 1,13500,371,371,371
BEGIN DESCRIPTION:
SANFERNANDO015 26.0
END DESCRIPTION:
XS GIS Cut Line= 3
      2740755.64     10288253.10      2740369.46     10288153.57
      2739855.66     10288403.12
#Sta/Elev= 30
  4601.2 1417.23  4603.7 1417.23  4664.8 1410.26  4704.6 1407.64  4741.0 1404.46
  4746.1 1405.01  4776.5 1402.72  4781.7 1403.15  4898.6 1395.23  4903.7 1395.64
  4921.3 1393.57  4939.2 1389.54  4944.4 1390.65  4960.6 1387.73  4960.8 1387.23
  4964.6 1387.73  4979.9 1388.34  4993.6 1390.79  4999.4 1393.92  5010.1 1394.63
  5015.6 1393.53  5032.6 1395.96  5151.0 1398.57  5213.1 1398.75  5218.7 1399.84
  5280.8 1400.74  5371.1 1404.85  5393.3 1406.83  5437.8 1407.91  5571.2 1415.55
#Mann=5,-1,0
  4601.2    0.05       0  4603.7    0.12       0  4704.6    0.05       0
  4960.6    0.05       0  4964.6    0.05       0
Bank Sta=4960.6,4964.6
Exp/Cntr=0.3,0.1

Type RM Length L Ch R = 1,13129,767,767,767
BEGIN DESCRIPTION:
Mapping XS c51ba779
END DESCRIPTION:
XS GIS Cut Line= 2
      2740661.49     10287720.44      2739911.54     10287904.46
#Sta/Elev= 30
  4618.3 1395.44  4650.3 1394.81  4655.4 1395.50  4691.8 1394.77  4697.0 1395.15
  4733.4 1393.78  4758.1 1394.24  4775.0 1393.31  4780.1 1393.79  4816.6 1392.74
  4830.2 1393.24  4904.9 1392.07  4953.8 1389.55  4993.0 1385.58  4993.2 1385.08
  4996.7 1385.08  4997.0 1385.58  5005.3 1386.54  5024.4 1390.18  5036.1 1390.97
  5112.7 1392.53  5128.8 1393.65  5154.3 1394.23  5159.7 1395.15  5195.9 1397.18
  5252.4 1399.16  5314.2 1402.69  5320.6 1403.50  5367.3 1405.49  5390.5 1405.36
#Mann=3,-1,0
  4618.3    0.05       0  4993.0    0.05       0  4997.0    0.05       0
Bank Sta=4993,4997
Exp/Cntr=0.3,0.1

Type RM Length L Ch R = 1,12362,133,133,133
BEGIN DESCRIPTION:
Mapping XS c098fa4e
END DESCRIPTION:
XS GIS Cut Line= 2
      2740887.17     10287175.30      2740099.86     10287192.64
#Sta/Elev= 30
  4673.9 1408.62  4705.4 1409.25  4735.4 1409.26  4785.4 1405.02  4795.4 1403.94
  4801.1 1402.62  4806.1 1402.99  4825.4 1399.93  4855.4 1396.26  4865.4 1394.69
  4895.4 1391.49  4915.4 1388.54  4935.4 1386.27  4945.5 1384.03  5003.5 1383.68
  5003.7 1383.18  5007.2 1383.18  5007.5 1383.68  5100.9 1384.13  5175.5 1383.81
  5245.5 1384.15  5253.2 1384.93  5258.2 1384.82  5295.5 1386.16  5325.5 1388.89
  5365.6 1390.87  5415.6 1393.98  5425.6 1394.93  5455.6 1395.76  5461.4 1396.58
#Mann=4,-1,0
  4673.9    0.12       0  5003.5    0.07       0  5007.5    0.12       0
  5100.9    0.05       0
Bank Sta=5003.5,5007.5
Exp/Cntr=0.3,0.1

Type RM Length L Ch R = 1,12229,341,341,341
BEGIN DESCRIPTION:
Mapping XS 77b7974d
END DESCRIPTION:
XS GIS Cut Line= 4
      2740921.92     10287081.55      2740567.77     10287060.71
      2740234.44     10287088.49      2739964.00     10287168.23
#Sta/Elev= 30
  4592.2 1402.09  4647.1 1404.19  4652.1 1403.63  4688.6 1403.77  4758.7 1400.44
  4808.4 1395.83  4817.4 1394.68  4822.4 1395.14  4868.9 1389.32  4907.1 1386.00
  4959.1 1382.01  4979.2 1379.43  4987.2 1377.56  4987.4 1377.06  4991.2 1377.56
  5006.3 1378.78  5019.3 1380.39  5049.4 1382.27  5109.6 1381.90  5205.3 1383.07
  5240.1 1381.83  5250.1 1384.06  5270.2 1384.50  5387.9 1390.62  5447.0 1394.75
  5493.1 1399.59  5509.5 1400.20  5526.4 1401.88  5559.7 1402.80  5563.4 1403.51
#Mann=7,-1,0
  4592.2    0.05       0  4808.4    0.12       0  4907.1    0.05       0
  4987.2    0.05       0  4991.2    0.05       0  5006.3    0.12       0
  5205.3    0.05       0
Bank Sta=4987.2,4991.2
Exp/Cntr=0.3,0.1

Type RM Length L Ch R = 1,11888,342,342,342
BEGIN DESCRIPTION:
Mapping XS 8023d5a6
END DESCRIPTION:
XS GIS Cut Line= 2
      2740950.76     10286684.67      2739858.84     10286799.06
#Sta/Elev= 30
  4457.2 1388.80  4532.7 1388.09  4653.3 1385.72  4713.7 1385.55  4804.2 1384.07
  4965.0 1378.12  4970.1 1377.14  4985.2 1376.14  4993.2 1374.09  4993.5 1373.59
  4997.0 1373.59  4997.2 1374.09  5005.3 1374.91  5015.3 1377.43  5025.4 1378.26
  5045.5 1378.58  5055.5 1378.14  5063.3 1378.80  5085.7 1377.79  5156.1 1377.96
  5161.6 1377.49  5196.3 1377.57  5216.4 1376.79  5236.5 1377.59  5347.1 1379.29
  5367.2 1380.32  5427.6 1381.48  5508.0 1384.05  5538.2 1384.24  5555.1 1385.08
#Mann=3,-1,0
  4457.2    0.05       0  4993.2    0.03       0  4997.2    0.05       0
Bank Sta=4993.2,4997.2
Exp/Cntr=0.3,0.1

Type RM Length L Ch R = 1,11546,365,365,365
BEGIN DESCRIPTION:
Mapping XS d069a8ae
END DESCRIPTION:
XS GIS Cut Line= 4
      2741190.29     10286590.90      2740622.63     10286351.34
      2740195.55     10286445.09      2739674.68     10286814.91
#Sta/Elev= 30
  4156.0 1389.02  4294.2 1386.89  4378.1 1387.21  4447.4 1385.50  4660.3 1384.56
  4677.1 1383.52  4804.3 1380.83  4963.5 1375.86  4984.0 1373.55  4989.7 1371.09
  4992.8 1370.92  4993.1 1370.42  4996.6 1370.42  4996.8 1370.92  5014.7 1372.56
  5038.6 1373.61  5045.4 1374.61  5087.5 1375.57  5158.1 1375.64  5229.8 1373.61
  5250.7 1374.67  5307.3 1374.23  5357.7 1375.16  5387.2 1374.51  5437.6 1375.94
  5488.1 1376.28  5544.7 1378.62  5675.1 1382.03  5761.1 1385.58  5848.2 1388.02
#Mann=3,-1,0
  4156.0    0.05       0  4992.8    0.03       0  4996.8    0.05       0
Bank Sta=4992.8,4996.8
Exp/Cntr=0.3,0.1

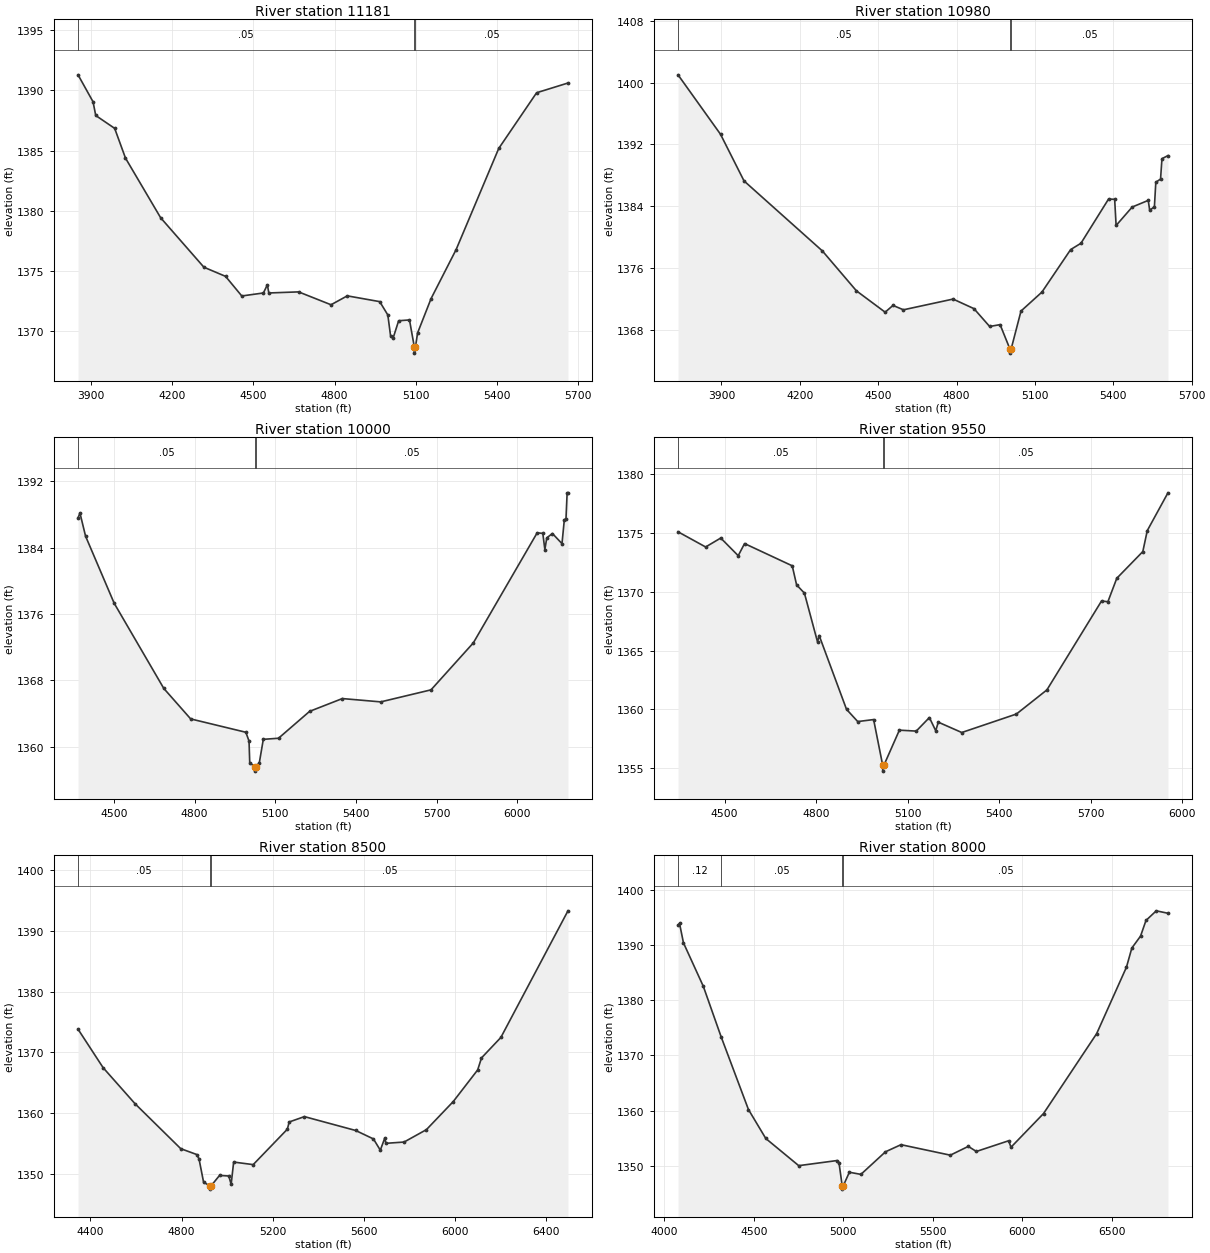
Type RM Length L Ch R = 1,11181,201,201,201
BEGIN DESCRIPTION:
Mapping XS b79e3574
END DESCRIPTION:
XS GIS Cut Line= 2
      2741461.14     10286018.01      2739649.68     10286070.06
#Sta/Elev= 30
  3851.3 1391.30  3906.8 1389.06  3916.8 1387.92  3986.8 1386.85  4026.8 1384.38
  4156.9 1379.42  4316.9 1375.31  4397.0 1374.55  4457.0 1372.92  4537.0 1373.17
  4551.6 1373.85  4557.0 1373.17  4667.1 1373.26  4787.1 1372.19  4847.2 1372.93
  4967.2 1372.45  4997.2 1371.34  5007.2 1369.63  5017.2 1369.45  5037.2 1370.86
  5077.3 1370.93  5095.3 1368.67  5095.5 1368.17  5099.3 1368.67  5107.3 1369.85
  5157.3 1372.71  5249.9 1376.78  5407.4 1385.18  5547.5 1389.81  5663.5 1390.62
#Mann=3,-1,0
  3851.3    0.05       0  5095.3    0.03       0  5099.3    0.05       0
Bank Sta=5095.3,5099.3
Exp/Cntr=0.3,0.1

Type RM Length L Ch R = 1,10980,980,980,980
BEGIN DESCRIPTION:
Mapping XS 89fcae76
END DESCRIPTION:
XS GIS Cut Line= 3
      2741518.42     10285866.96      2739971.59     10285877.38
      2739670.07     10286007.34
#Sta/Elev= 30
  3734.0 1401.00  3896.7 1393.30  3986.7 1387.26  4286.7 1378.19  4416.8 1373.03
  4526.8 1370.26  4556.8 1371.14  4596.8 1370.57  4786.8 1371.96  4866.8 1370.72
  4926.8 1368.41  4966.8 1368.65  5004.8 1365.46  5005.0 1364.96  5008.8 1365.46
  5046.8 1370.41  5126.8 1372.86  5236.8 1378.37  5276.3 1379.19  5381.8 1384.91
  5405.3 1384.88  5410.8 1381.49  5472.4 1383.88  5533.8 1384.74  5539.3 1383.47
  5557.4 1383.91  5562.8 1387.09  5580.9 1387.50  5586.3 1390.14  5609.2 1390.54
#Mann=3,-1,0
  3734.0    0.05       0  5004.8    0.03       0  5008.8    0.05       0
Bank Sta=5004.8,5008.8
Exp/Cntr=0.3,0.1

Type RM Length L Ch R = 1,10000,450,450,450
BEGIN DESCRIPTION:
SANFERNANDO015 19.0
END DESCRIPTION:
XS GIS Cut Line= 3
      2740755.67     10284553.13      2740343.73     10285034.68
      2739655.67     10286003.14
#Sta/Elev= 30
  4366.3 1387.57  4373.4 1388.16  4394.3 1385.37  4500.7 1377.29  4685.2 1367.03
  4785.1 1363.36  4990.3 1361.75  5002.1 1360.69  5004.7 1358.10  5023.6 1357.57
  5023.9 1357.07  5027.6 1357.57  5040.4 1358.08  5055.2 1360.90  5111.7 1361.03
  5227.4 1364.27  5349.1 1365.81  5491.8 1365.41  5678.8 1366.86  5836.2 1372.52
  6073.6 1385.78  6094.5 1385.70  6102.1 1383.76  6109.3 1385.17  6130.2 1385.69
  6165.8 1384.47  6174.5 1387.36  6180.6 1387.42  6184.9 1390.59  6188.0 1390.59
#Mann=3,-1,0
  4366.3    0.05       0  5023.6    0.05       0  5027.6    0.05       0
Bank Sta=5023.6,5027.6
Exp/Cntr=0.3,0.1

Type RM Length L Ch R = 1,9550,1050,1050,1050
BEGIN DESCRIPTION:
Mapping XS d100324c
END DESCRIPTION:
XS GIS Cut Line= 4
      2740310.11     10284450.32      2740044.51     10284768.00
      2739929.92     10285111.75      2739430.29     10285772.73
#Sta/Elev= 30
  4347.6 1375.09  4438.1 1373.80  4487.6 1374.56  4544.8 1373.06  4565.6 1374.09
  4721.8 1372.20  4736.1 1370.58  4761.7 1369.88  4804.7 1365.73  4810.0 1366.28
  4899.6 1360.01  4936.4 1358.97  4988.4 1359.14  5018.1 1355.26  5018.3 1354.76
  5022.1 1355.26  5072.8 1358.24  5128.0 1358.16  5171.1 1359.31  5191.9 1358.19
  5200.2 1358.92  5277.2 1358.04  5456.2 1359.61  5556.1 1361.66  5735.0 1369.21
  5755.9 1369.15  5785.0 1371.14  5870.3 1373.41  5884.9 1375.19  5952.6 1378.40
#Mann=3,-1,0
  4347.6    0.05       0  5018.1    0.05       0  5022.1    0.05       0
Bank Sta=5018.1,5022.1
Exp/Cntr=0.3,0.1

Type RM Length L Ch R = 1,8500,500,500,500
BEGIN DESCRIPTION:
SANFERNANDO015 17.0
END DESCRIPTION:
XS GIS Cut Line= 3
      2740105.64     10284553.11      2739451.96     10284520.24
      2738055.69     10285053.11
#Sta/Elev= 30
  4345.5 1373.81  4455.6 1367.48  4595.8 1361.55  4796.0 1354.17  4866.1 1353.21
  4876.1 1352.50  4896.1 1348.68  4924.2 1348.02  4924.4 1347.52  4928.2 1348.02
  4966.2 1349.77  5006.7 1349.68  5017.1 1348.31  5028.1 1351.97  5113.8 1351.55
  5263.6 1357.37  5271.7 1358.56  5338.5 1359.44  5563.3 1357.16  5641.3 1355.77
  5671.4 1353.92  5690.8 1355.90  5696.1 1355.05  5775.7 1355.26  5873.7 1357.30
  5991.4 1361.92  6098.5 1367.12  6115.2 1369.09  6200.1 1372.45  6494.5 1393.27
#Mann=3,-1,0
  4345.5    0.05       0  4924.2    0.05       0  4928.2    0.05       0
Bank Sta=4924.2,4928.2
Exp/Cntr=0.3,0.1

Type RM Length L Ch R = 1,8000,500,500,500
BEGIN DESCRIPTION:
SANFERNANDO015 16.0
END DESCRIPTION:
XS GIS Cut Line= 3
      2740305.72     10283653.09      2739484.38     10284075.51
      2737955.65     10285053.14
#Sta/Elev= 30
  4076.4 1393.55  4084.7 1393.91  4106.9 1390.37  4217.8 1382.50  4317.0 1373.39
  4470.0 1360.19  4567.0 1354.94  4751.1 1350.02  4966.2 1350.95  4976.0 1350.58
  4994.5 1346.27  4994.7 1345.77  4998.5 1346.27  5034.1 1348.83  5098.5 1348.44
  5235.9 1352.53  5322.6 1353.82  5598.3 1351.92  5698.8 1353.51  5743.8 1352.59
  5924.3 1354.53  5937.5 1353.36  6119.3 1359.46  6416.2 1373.93  6582.8 1385.97
  6612.8 1389.43  6661.5 1391.59  6691.9 1394.43  6749.4 1396.17  6814.6 1395.73
#Mann=4,-1,0
  4076.4    0.12       0  4317.0    0.05       0  4994.5    0.05       0
  4998.5    0.05       0
Bank Sta=4994.5,4998.5
Exp/Cntr=0.3,0.1

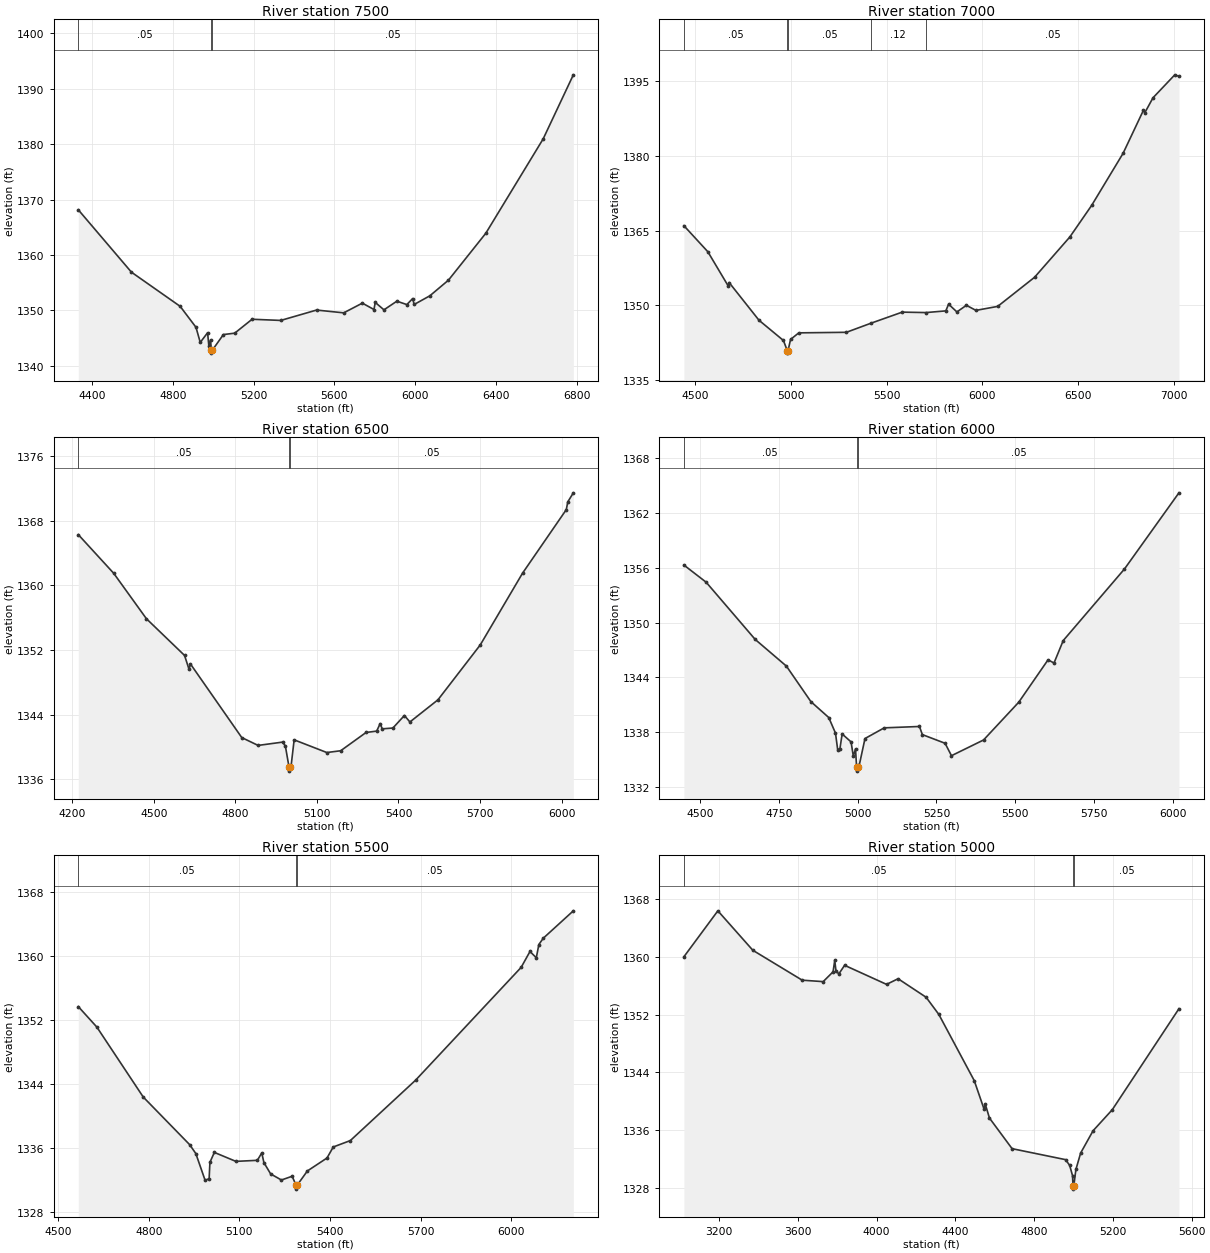
Type RM Length L Ch R = 1,7500,500,500,500
BEGIN DESCRIPTION:
SANFERNANDO015 15.0
END DESCRIPTION:
XS GIS Cut Line= 3
      2739855.70     10283203.09      2739435.73     10283723.32
      2738055.70     10284853.10
#Sta/Elev= 30
  4331.4 1368.15  4594.5 1356.90  4836.0 1350.73  4914.4 1346.95  4935.5 1344.22
  4971.9 1345.97  4978.3 1343.51  4986.3 1344.66  4990.7 1342.79  4991.0 1342.29
  4994.7 1342.79  5050.1 1345.64  5106.1 1345.89  5192.2 1348.40  5334.3 1348.19
  5511.6 1350.06  5646.2 1349.56  5738.4 1351.31  5795.9 1350.16  5802.3 1351.44
  5845.4 1350.10  5909.3 1351.66  5958.8 1351.05  5987.5 1352.13  5995.2 1351.07
  6072.7 1352.63  6164.8 1355.45  6350.0 1363.92  6634.2 1380.95  6783.5 1392.50
#Mann=3,-1,0
  4331.4    0.05       0  4990.7    0.03       0  4994.7    0.05       0
Bank Sta=4990.7,4994.7
Exp/Cntr=0.3,0.1

Type RM Length L Ch R = 1,7000,500,500,500
BEGIN DESCRIPTION:
SANFERNANDO015 14.0
END DESCRIPTION:
XS GIS Cut Line= 3
      2739705.70     10283053.10      2739206.49     10283306.63
      2737955.70     10284903.10
#Sta/Elev= 30
  4440.1 1365.97  4565.3 1360.74  4671.0 1353.92  4676.6 1354.56  4832.7 1346.99
  4960.4 1342.93  4980.6 1340.89  4980.9 1340.39  4984.6 1340.89  4997.7 1343.14
  5040.9 1344.46  5289.6 1344.57  5417.0 1346.38  5581.6 1348.62  5705.3 1348.53
  5809.4 1348.87  5823.9 1350.22  5867.3 1348.66  5917.0 1349.99  5966.7 1348.97
  6080.6 1349.77  6273.2 1355.61  6457.7 1363.70  6571.6 1370.03  6735.9 1380.48
  6842.8 1389.16  6850.3 1388.68  6892.5 1391.64  7006.4 1396.25  7028.1 1395.95
#Mann=5,-1,0
  4440.1    0.05       0  4980.6    0.05       0  4984.6    0.05       0
  5417.0    0.12       0  5705.3    0.05       0
Bank Sta=4980.6,4984.6
Exp/Cntr=0.3,0.1

Type RM Length L Ch R = 1,6500,500,500,500
BEGIN DESCRIPTION:
SANFERNANDO015 13.0
END DESCRIPTION:
XS GIS Cut Line= 3
      2739705.67     10282953.11      2738929.82     10282905.58
      2737905.70     10283103.11
#Sta/Elev= 30
  4222.7 1366.28  4352.9 1361.50  4473.2 1355.88  4613.4 1351.34  4630.0 1349.62
  4635.0 1350.29  4823.8 1341.18  4883.9 1340.21  4974.1 1340.62  4984.1 1340.14
  4997.6 1337.53  4997.8 1337.03  5001.6 1337.53  5004.7 1337.53  5016.4 1340.90
  5136.6 1339.33  5187.5 1339.55  5280.8 1341.81  5319.9 1341.98  5332.7 1342.91
  5340.3 1342.26  5379.5 1342.36  5421.8 1343.91  5442.1 1343.11  5545.2 1345.85
  5700.8 1352.64  5856.4 1361.52  6017.1 1369.37  6022.6 1370.33  6043.0 1371.45
#Mann=3,-1,0
  4222.7    0.05       0  4997.6    0.03       0  5001.6    0.05       0
Bank Sta=4997.6,5001.6
Exp/Cntr=0.3,0.1

Type RM Length L Ch R = 1,6000,500,500,500
BEGIN DESCRIPTION:
SANFERNANDO015 12.0
END DESCRIPTION:
XS GIS Cut Line= 3
      2739455.70     10282853.12      2739058.51     10282470.65
      2738055.67     10282653.11
#Sta/Elev= 30
  4448.6 1356.31  4519.2 1354.43  4674.9 1348.16  4773.9 1345.24  4851.6 1341.35
  4908.2 1339.61  4929.6 1337.90  4936.5 1336.10  4943.7 1336.20  4950.7 1337.81
  4979.0 1336.94  4986.2 1335.37  4993.1 1336.17  4996.5 1334.24  4996.7 1333.74
  5000.5 1334.24  5004.0 1334.24  5023.2 1337.31  5084.2 1338.48  5196.0 1338.63
  5205.2 1337.74  5277.3 1336.79  5297.6 1335.43  5399.3 1337.15  5511.1 1341.29
  5604.0 1345.93  5622.9 1345.58  5652.2 1348.04  5846.5 1355.88  6019.3 1364.22
#Mann=3,-1,0
  4448.6    0.05       0  4996.5    0.05       0  5000.5    0.05       0
Bank Sta=4996.5,5000.5
Exp/Cntr=0.3,0.1

Type RM Length L Ch R = 1,5500,500,500,500
BEGIN DESCRIPTION:
SANFERNANDO015 11.0
END DESCRIPTION:
XS GIS Cut Line= 3
      2739605.69     10282103.11      2739182.66     10282009.78
      2738205.65     10281303.09
#Sta/Elev= 30
  4566.8 1353.63  4628.2 1351.07  4781.9 1342.32  4935.5 1336.37  4955.9 1335.26
  4986.7 1331.91  5000.0 1332.12  5002.6 1334.16  5017.3 1335.40  5088.5 1334.28
  5159.6 1334.41  5174.3 1335.34  5181.4 1334.12  5203.7 1332.71  5239.3 1331.95
  5274.9 1332.42  5287.6 1331.31  5287.9 1330.81  5291.6 1331.31  5325.2 1333.08
  5390.2 1334.70  5411.0 1336.08  5467.5 1336.88  5683.3 1344.42  6033.0 1358.53
  6062.3 1360.52  6083.2 1359.73  6091.7 1361.39  6106.4 1362.18  6205.8 1365.60
#Mann=3,-1,0
  4566.8    0.05       0  5287.6    0.05       0  5291.6    0.05       0
Bank Sta=5287.6,5291.6
Exp/Cntr=0.3,0.1

Type RM Length L Ch R = 1,5000,500,500,500
BEGIN DESCRIPTION:
SANFERNANDO015 10.0
END DESCRIPTION:
XS GIS Cut Line= 3
      2740655.70     10282753.12      2739060.00     10281583.09
      2738555.65     10281403.10
#Sta/Elev= 30
  3021.3 1359.99  3193.8 1366.35  3371.4 1360.89  3622.2 1356.75  3728.7 1356.55
  3778.9 1357.91  3787.4 1359.50  3793.6 1358.05  3808.2 1357.62  3837.5 1358.81
  4050.6 1356.17  4109.2 1356.95  4251.3 1354.39  4316.1 1352.01  4495.9 1342.85
  4546.1 1338.88  4552.3 1339.56  4573.1 1337.67  4688.1 1333.43  4959.8 1331.91
  4980.7 1331.11  4995.3 1329.67  4997.4 1328.33  4997.7 1327.83  5001.7 1328.33
  5012.3 1330.56  5036.4 1332.83  5099.4 1335.91  5197.2 1338.83  5535.5 1352.80
#Mann=3,-1,0
  3021.3    0.05       0  4997.4    0.05       0  5001.7    0.05       0
Bank Sta=4997.4,5001.7
Exp/Cntr=0.3,0.1

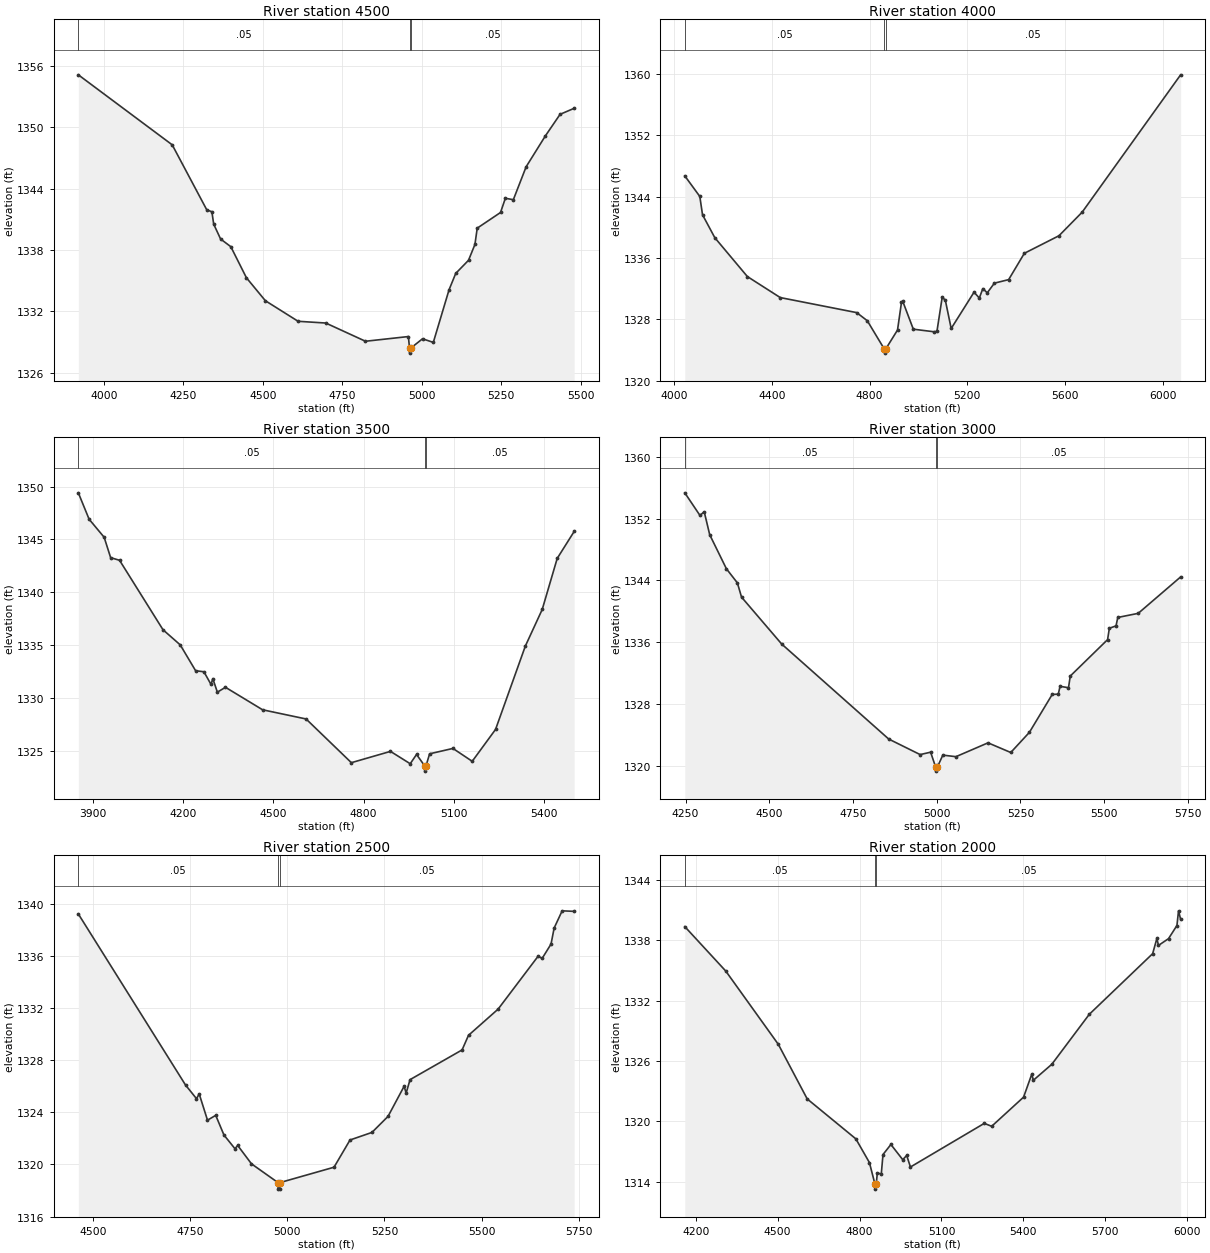
Type RM Length L Ch R = 1,4500,500,500,500
BEGIN DESCRIPTION:
SANFERNANDO015 9.0
END DESCRIPTION:
XS GIS Cut Line= 3
      2739705.67     10282053.08      2739182.14     10281108.57
      2738705.65     10281053.11
#Sta/Elev= 30
  3920.1 1355.11  4215.4 1348.27  4324.1 1341.92  4340.2 1341.73  4345.9 1340.52
  4367.6 1339.07  4399.7 1338.32  4448.9 1335.28  4508.4 1333.04  4611.4 1331.03
  4698.4 1330.86  4823.3 1329.08  4958.3 1329.54  4961.8 1328.42  4962.1 1327.92
  4966.2 1328.42  5002.7 1329.32  5036.7 1328.97  5086.2 1334.11  5107.2 1335.71
  5147.4 1336.99  5167.6 1338.54  5174.8 1340.13  5248.1 1341.66  5263.3 1343.05
  5288.4 1342.91  5328.7 1346.13  5389.1 1349.14  5435.4 1351.25  5479.7 1351.84
#Mann=3,-1,0
  3920.1    0.05       0  4961.8    0.05       0  4966.2    0.05       0
Bank Sta=4961.8,4966.2
Exp/Cntr=0.3,0.1

Type RM Length L Ch R = 1,4000,500,500,500
BEGIN DESCRIPTION:
SANFERNANDO015 8.0
END DESCRIPTION:
XS GIS Cut Line= 3
      2739605.69     10281603.14      2739395.72     10280669.67
      2738405.68     10280253.11
#Sta/Elev= 30
  4043.2 1346.71  4104.7 1344.03  4115.8 1341.64  4166.2 1338.65  4299.5 1333.59
  4434.2 1330.85  4747.4 1328.89  4790.7 1327.83  4861.0 1324.11  4861.3 1323.61
  4865.5 1324.11  4914.5 1326.62  4930.8 1330.24  4936.0 1330.36  4979.2 1326.73
  5065.1 1326.39  5076.0 1326.45  5097.7 1330.93  5110.6 1330.47  5134.3 1326.82
  5227.9 1331.55  5249.6 1330.79  5263.9 1332.02  5282.1 1331.47  5311.3 1332.73
  5369.7 1333.19  5434.0 1336.62  5575.9 1338.91  5670.8 1341.98  6074.1 1359.88
#Mann=3,-1,0
  4043.2    0.05       0  4861.0    0.03       0  4865.5    0.05       0
Bank Sta=4861,4865.5
Exp/Cntr=0.3,0.1

Type RM Length L Ch R = 1,3500,500,500,500
BEGIN DESCRIPTION:
SANFERNANDO015 7.0
END DESCRIPTION:
XS GIS Cut Line= 3
      2740755.73     10281003.14      2739793.40     10280373.70
      2739455.67     10280003.10
#Sta/Elev= 30
  3850.1 1349.42  3886.0 1346.92  3936.1 1345.21  3957.7 1343.28  3987.4 1343.03
  4132.1 1336.45  4189.4 1335.02  4240.7 1332.57  4268.4 1332.47  4292.0 1331.27
  4298.0 1331.82  4313.1 1330.54  4340.2 1331.00  4463.8 1328.87  4608.6 1328.00
  4759.4 1323.86  4889.7 1324.93  4955.4 1323.76  4976.5 1324.64  5003.5 1323.56
  5003.8 1323.06  5008.0 1323.56  5020.0 1324.70  5097.7 1325.21  5161.9 1323.99
  5239.6 1327.01  5338.9 1334.91  5395.0 1338.37  5445.0 1343.21  5501.4 1345.76
#Mann=3,-1,0
  3850.1    0.05       0  5003.5    0.03       0  5008.0    0.05       0
Bank Sta=5003.5,5008
Exp/Cntr=0.3,0.1

Type RM Length L Ch R = 1,3000,500,500,500
BEGIN DESCRIPTION:
SANFERNANDO015 6.0
END DESCRIPTION:
XS GIS Cut Line= 3
      2740905.69     10280503.12      2740239.56     10280153.73
      2739555.73     10279903.13
#Sta/Elev= 30
  4247.8 1355.33  4293.0 1352.41  4305.8 1352.88  4322.2 1349.91  4372.0 1345.51
  4404.8 1343.68  4417.2 1341.84  4537.1 1335.77  4856.7 1323.48  4950.5 1321.47
  4981.8 1321.78  4997.0 1319.83  4997.4 1319.33  5001.7 1319.83  5018.2 1321.40
  5057.4 1321.20  5153.2 1322.99  5221.1 1321.74  5276.8 1324.35  5344.9 1329.25
  5363.0 1329.29  5368.3 1330.30  5393.5 1330.12  5398.8 1331.63  5510.2 1336.34
  5515.5 1337.81  5535.4 1338.12  5540.7 1339.21  5601.7 1339.74  5728.3 1344.45
#Mann=3,-1,0
  4247.8    0.05       0  4997.0    0.05       0  5001.7    0.05       0
Bank Sta=4997,5001.7
Exp/Cntr=0.3,0.1

Type RM Length L Ch R = 1,2500,500,500,500
BEGIN DESCRIPTION:
SANFERNANDO015 5.0
END DESCRIPTION:
XS GIS Cut Line= 3
      2740855.71     10280103.13      2740472.23     10279725.93
      2739755.71     10279903.10
#Sta/Elev= 30
  4462.1 1339.22  4737.9 1326.10  4766.2 1325.05  4773.2 1325.41  4794.5 1323.40
  4815.7 1323.77  4836.9 1322.26  4865.2 1321.21  4872.2 1321.46  4907.7 1320.05
  4976.0 1318.61  4976.3 1318.11  4980.4 1318.11  4980.8 1318.61  5120.1 1319.79
  5161.3 1321.88  5217.7 1322.46  5259.1 1323.69  5300.5 1326.00  5305.7 1325.48
  5315.8 1326.51  5449.7 1328.79  5466.2 1329.91  5542.4 1331.92  5645.4 1335.98
  5655.7 1335.81  5678.6 1336.91  5686.6 1338.14  5707.2 1339.46  5738.1 1339.42
#Mann=3,-1,0
  4462.1    0.05       0  4976.0    0.05       0  4980.8    0.05       0
Bank Sta=4976,4980.8
Exp/Cntr=0.3,0.1

Type RM Length L Ch R = 1,2000,500,500,500
BEGIN DESCRIPTION:
SANFERNANDO015 4.0
END DESCRIPTION:
XS GIS Cut Line= 3
      2741055.67     10279903.10      2740537.04     10279242.33
      2739705.71     10279753.09
#Sta/Elev= 30
  4160.0 1339.37  4310.0 1334.95  4502.5 1327.66  4608.3 1322.23  4786.4 1318.26
  4836.1 1315.90  4856.3 1313.76  4856.6 1313.26  4861.1 1313.76  4865.0 1314.87
  4879.5 1314.76  4885.8 1316.70  4914.7 1317.70  4958.1 1316.19  4972.6 1316.61
  4986.3 1315.46  5256.7 1319.80  5283.8 1319.51  5400.6 1322.41  5430.6 1324.69
  5436.5 1324.09  5504.1 1325.68  5641.3 1330.65  5873.3 1336.68  5888.7 1338.19
  5894.6 1337.50  5931.3 1338.17  5962.2 1339.48  5968.0 1340.94  5975.7 1340.10
#Mann=3,-1,0
  4160.0    0.05       0  4856.3    0.03       0  4861.1    0.05       0
Bank Sta=4856.3,4861.1
Exp/Cntr=0.3,0.1