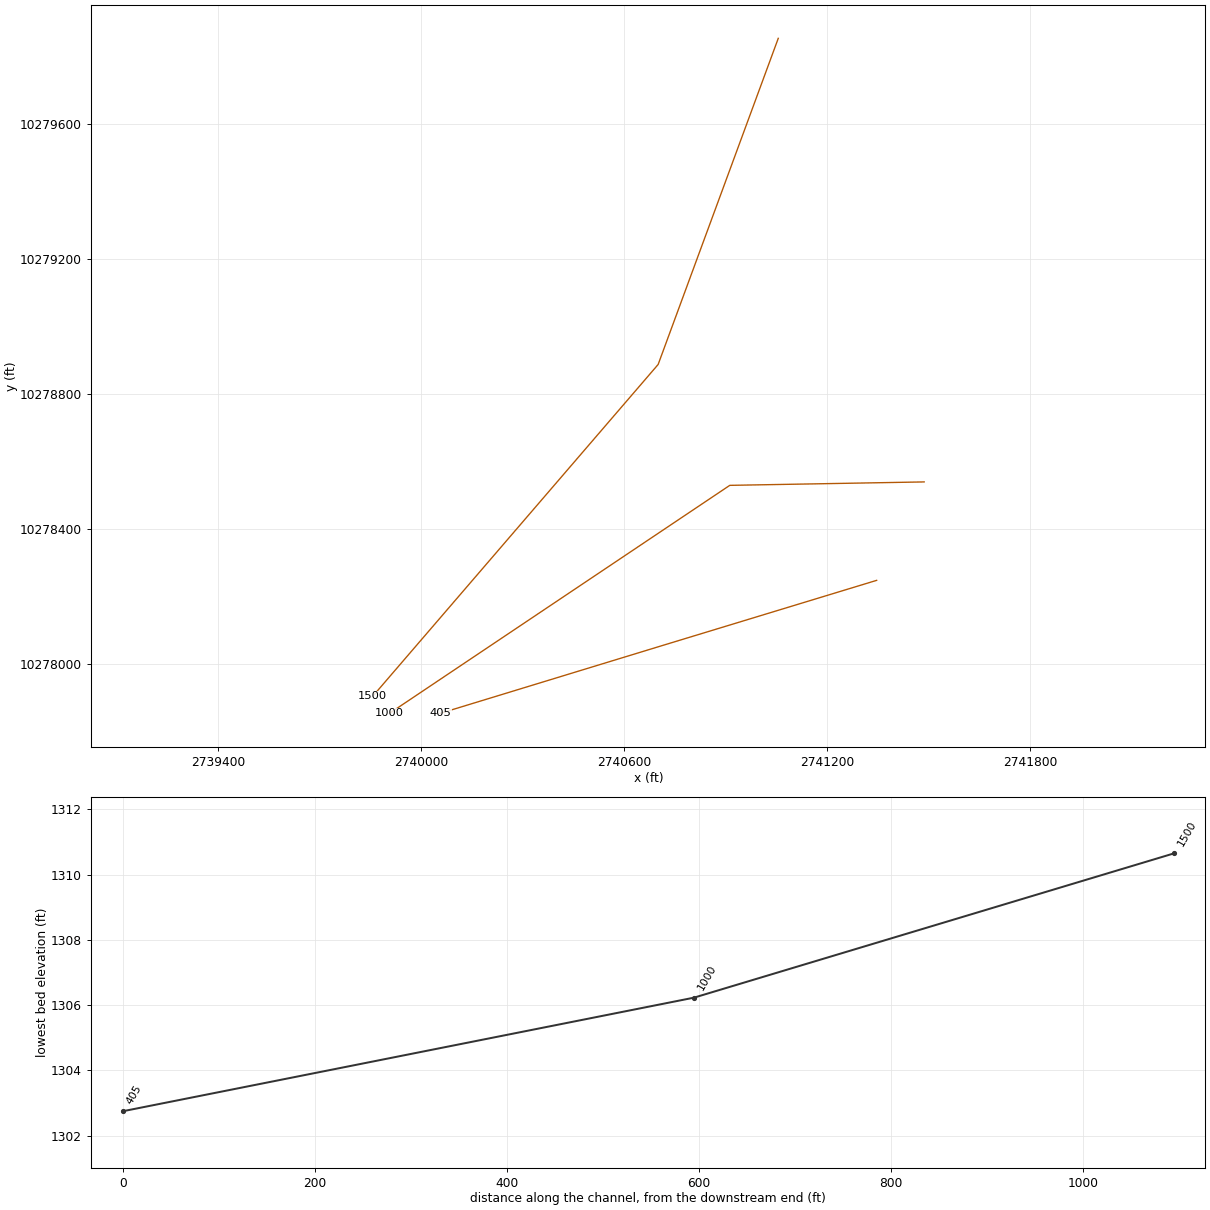
HEC-RAS study SANFERNANDO015.prj: SANFERNANDO015 Base Level Engineering

--- SANFERNANDO015.g01 (geometry) --- (continued)

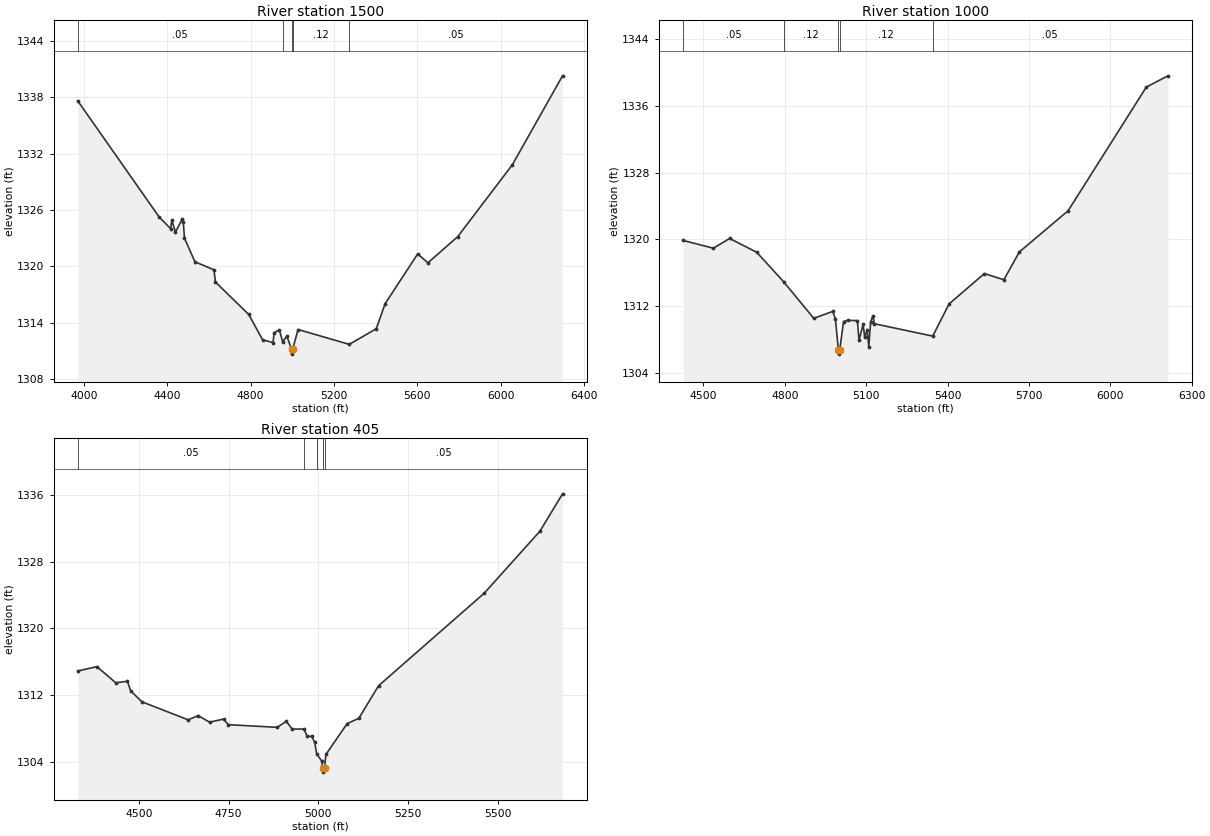
Type RM Length L Ch R = 1,1500,500,500,500
BEGIN DESCRIPTION:
SANFERNANDO015 3.0
END DESCRIPTION:
XS GIS Cut Line= 3
      2741055.67     10279853.09      2740700.40     10278886.83
      2739855.70     10277903.13
#Sta/Elev= 30
  3970.5 1337.60  4360.5 1325.26  4416.1 1324.00  4421.5 1324.91  4439.3 1323.64
  4471.2 1325.00  4477.1 1324.69  4482.4 1322.99  4532.7 1320.48  4624.1 1319.62
  4631.1 1318.32  4790.9 1314.87  4857.2 1312.18  4907.5 1311.88  4912.8 1312.93
  4938.0 1313.22  4953.8 1311.96  4973.8 1312.57  4996.5 1311.15  4996.9 1310.65
  5001.3 1311.15  5027.5 1313.27  5273.1 1311.69  5402.8 1313.35  5445.6 1316.03
  5601.4 1321.31  5650.8 1320.37  5793.5 1323.15  6055.7 1330.80  6296.6 1340.27
#Mann=5,-1,0
  3970.5    0.05       0  4953.8    0.12       0  4996.5    0.07       0
  5001.3    0.12       0  5273.1    0.05       0
Bank Sta=4996.5,5001.3
Exp/Cntr=0.3,0.1

Type RM Length L Ch R = 1,1000,595,595,595
BEGIN DESCRIPTION:
SANFERNANDO015 2.0
END DESCRIPTION:
XS GIS Cut Line= 3
      2741487.18     10278538.84      2740912.27     10278528.67
      2739905.66     10277853.10
#Sta/Elev= 30
  4425.0 1319.86  4536.5 1318.93  4596.5 1320.10  4696.5 1318.44  4795.8 1314.90
  4906.6 1310.52  4976.6 1311.35  4986.6 1310.43  4997.5 1306.73  4997.9 1306.23
  5002.4 1306.73  5016.5 1310.14  5031.4 1310.28  5067.5 1310.25  5073.5 1307.90
  5088.5 1309.82  5094.5 1308.24  5103.5 1309.16  5109.5 1307.13  5116.3 1310.09
  5124.5 1310.82  5130.5 1309.87  5345.3 1308.39  5405.4 1312.24  5535.6 1315.89
  5607.6 1315.15  5664.6 1318.48  5844.7 1323.43  6132.8 1338.25  6212.3 1339.60
#Mann=5,-1,0
  4425.0    0.05       0  4795.8    0.12       0  4997.5    0.07       0
  5002.4    0.12       0  5345.3    0.05       0
Bank Sta=4997.5,5002.4
Exp/Cntr=0.3,0.1

Type RM Length L Ch R = 1,405,0,0,0
BEGIN DESCRIPTION:
SANFERNANDO015 1.0
END DESCRIPTION:
XS GIS Cut Line= 3
      2741346.63     10278247.18      2740706.00     10278052.00
      2740055.73     10277853.13
#Sta/Elev= 30
  4330.3 1314.88  4383.6 1315.40  4435.8 1313.47  4468.4 1313.64  4477.6 1312.49
  4509.0 1311.18  4637.8 1309.02  4665.4 1309.53  4697.2 1308.74  4736.3 1309.11
  4749.4 1308.44  4885.3 1308.12  4910.9 1308.84  4927.2 1307.91  4960.3 1307.92
  4969.0 1307.03  4981.8 1307.04  4989.9 1306.34  4995.3 1304.97  5009.4 1304.08
  5012.1 1303.25  5012.5 1302.75  5017.3 1303.25  5021.2 1304.87  5080.2 1308.56
  5113.0 1309.21  5167.6 1313.10  5461.7 1324.19  5617.3 1331.65  5680.0 1336.12
#Mann=5,-1,0
  4330.3    0.05       0  4960.3    0.12       0  4995.3    0.05       0
  5012.1    0.05       0  5017.3    0.05       0
Bank Sta=5012.1,5017.3
Exp/Cntr=0.3,0.1

Chan Stop Cuts=-1