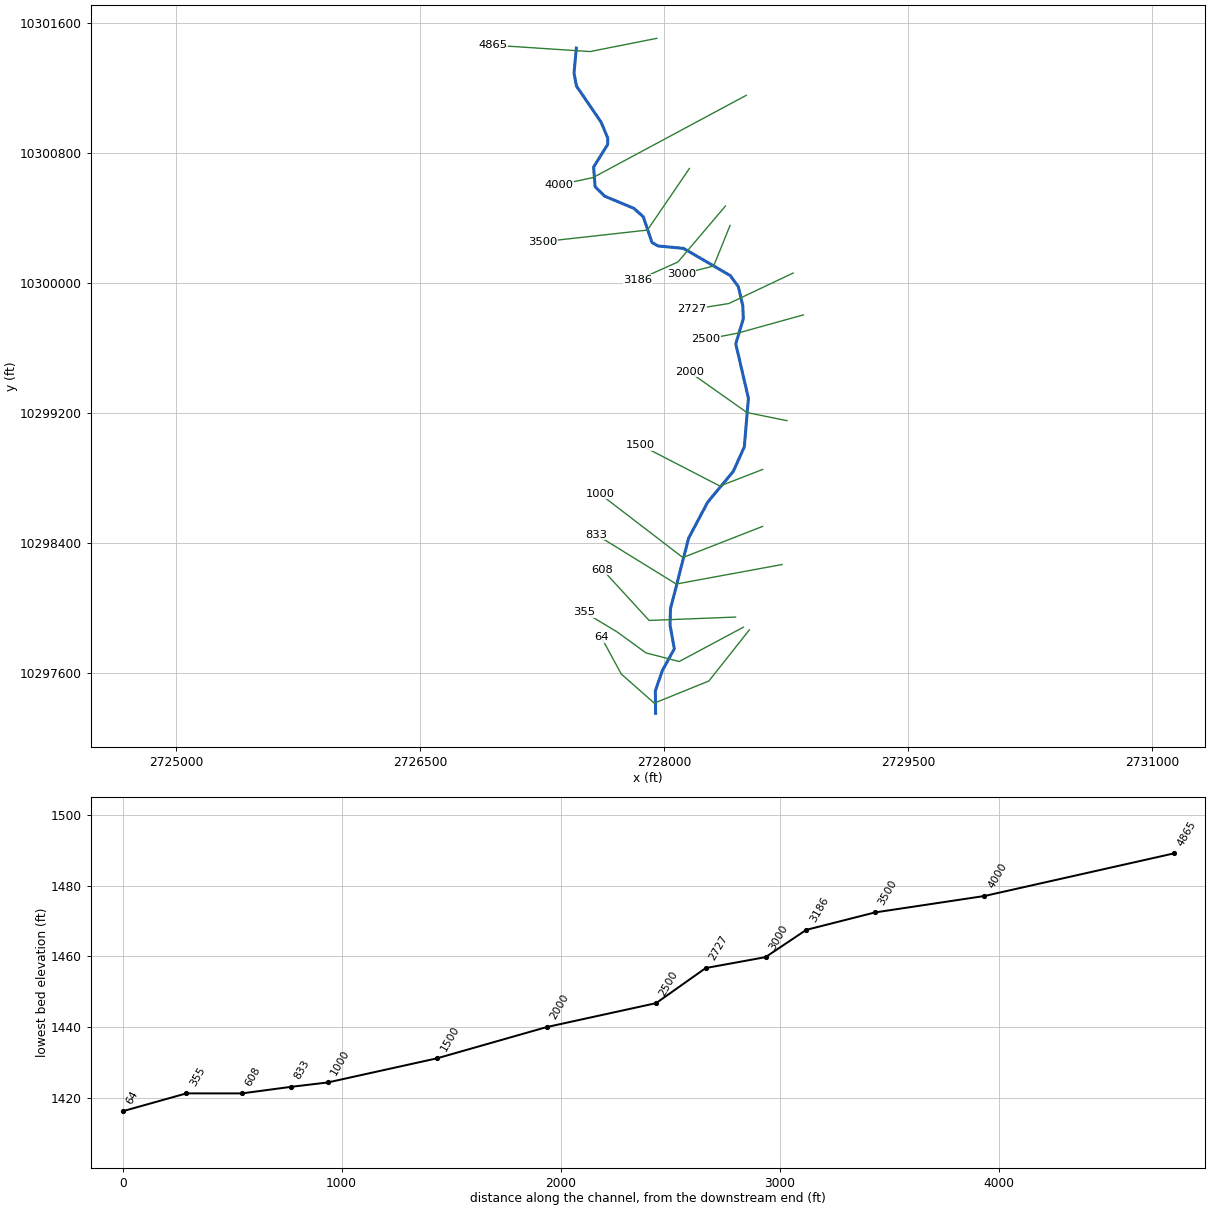
--- SANFERNANDO019.prj (project) ---

Proj Title=SANFERNANDO019 Base Level Engineering
Current Plan=p01
Default Exp/Contr=0.3,0.1
English Units
Geom File=g01
Flow File=f01
Plan File=p01
Y Axis Title=Elevation
X Axis Title(PF)=Main Channel Distance
X Axis Title(XS)=Station
BEGIN DESCRIPTION:
SANFERNANDO019
END DESCRIPTION:
DSS Export Rating Curves= 0
DSS Export Rating Curve Sorted= 0
DSS Export Volume Flow Curves= 0
DXF OffsetX= 0
DXF OffsetY= 0
DXF ScaleX= 1
DXF ScaleY= 10

--- SANFERNANDO019.p01 (plan) ---

Plan Title=Multiple Run
Short Identifier=Multiple
Geom File=g01
Flow File=f01
Subcritical Flow
K Sum by GR= 0
Std Step Tol= 0.01
Critical Tol= 0.01
Num of Std Step Trials= 20
Max Error Tol= 0.3
Flow Tol Ratio= 0.001
Split Flow NTrial= 30
Split Flow Tol= 0.02
Split Flow Ratio= 0.02
Log Output Level= 0
Friction Slope Method= 1
Unsteady Friction Slope Method= 2
Unsteady Bridges Friction Slope Method= 1
Parabolic Critical Depth
Global Vel Dist=  1 , 1 , 1
Global Log Level= 0
CheckData=True
Encroach Param= -1, 0, 0, 0
BEGIN DESCRIPTION:
Multiple Run
END DESCRIPTION:

--- SANFERNANDO019.f01 (steady flow) ---

Flow Title=Multiple
Program Version=4.10
Number of Profiles= 7
Profile Names=10-year,25-year,50-year,1pct_min,100-year,1pct_plu,500-year
River Rch & RM=SANFERNANDO019,Reach-1         ,4865
     755    1272    2660    1695    3814    8580    5544
River Rch & RM=SANFERNANDO019,Reach-1         ,64
    1180    2041    4447    3081    6474   13601    9362
Boundary for River Rch & Prof#=SANFERNANDO019,Reach-1         , 1
Up Type= 0
Dn Type= 3
Dn Slope=0.005
Boundary for River Rch & Prof#=SANFERNANDO019,Reach-1         , 2
Up Type= 0
Dn Type= 3
Dn Slope=0.005
Boundary for River Rch & Prof#=SANFERNANDO019,Reach-1         , 3
Up Type= 0
Dn Type= 3
Dn Slope=0.005
Boundary for River Rch & Prof#=SANFERNANDO019,Reach-1         , 4
Up Type= 0
Dn Type= 3
Dn Slope=0.005
Boundary for River Rch & Prof#=SANFERNANDO019,Reach-1         , 5
Up Type= 0
Dn Type= 3
Dn Slope=0.005
Boundary for River Rch & Prof#=SANFERNANDO019,Reach-1         , 6
Up Type= 0
Dn Type= 3
Dn Slope=0.005
Boundary for River Rch & Prof#=SANFERNANDO019,Reach-1         , 7
Up Type= 0
Dn Type= 3
Dn Slope=0.005
DSS Import GetInterval= 0
DSS Import GetPeak= 0
DSS Import FillOption= 0

--- SANFERNANDO019.g01 (geometry) ---

Geom Title=Existing Conditions
Program Version=4.10

River Reach=SANFERNANDO019  ,Reach-1
Reach XY= 30
      2727460.75       10301443.       2727446.5       10301289.
        2727462.       10301209.        2727613.       10300988.
       2727653.5       10300891.       2727653.5       10300851.
        2727567.       10300712.      2727576.25       10300591.
        2727635.       10300533.      2727814.75       10300458.
       2727872.5       10300406.      2727925.25       10300249.
      2727962.25       10300227.      2728119.75       10300212.
      2728406.75       10300045.      2728456.25       10299977.
        2728484.       10299860.        2728487.       10299779.
      2728440.75       10299625.       2728518.5       10299291.
      2728493.25       10298992.      2728425.25       10298841.
        2728268.       10298652.       2728150.5       10298430.
       2728039.5       10297997.      2728036.75       10297897.
        2728063.       10297751.      2727989.25       10297617.
       2727946.5       10297493.        2727948.       10297354.

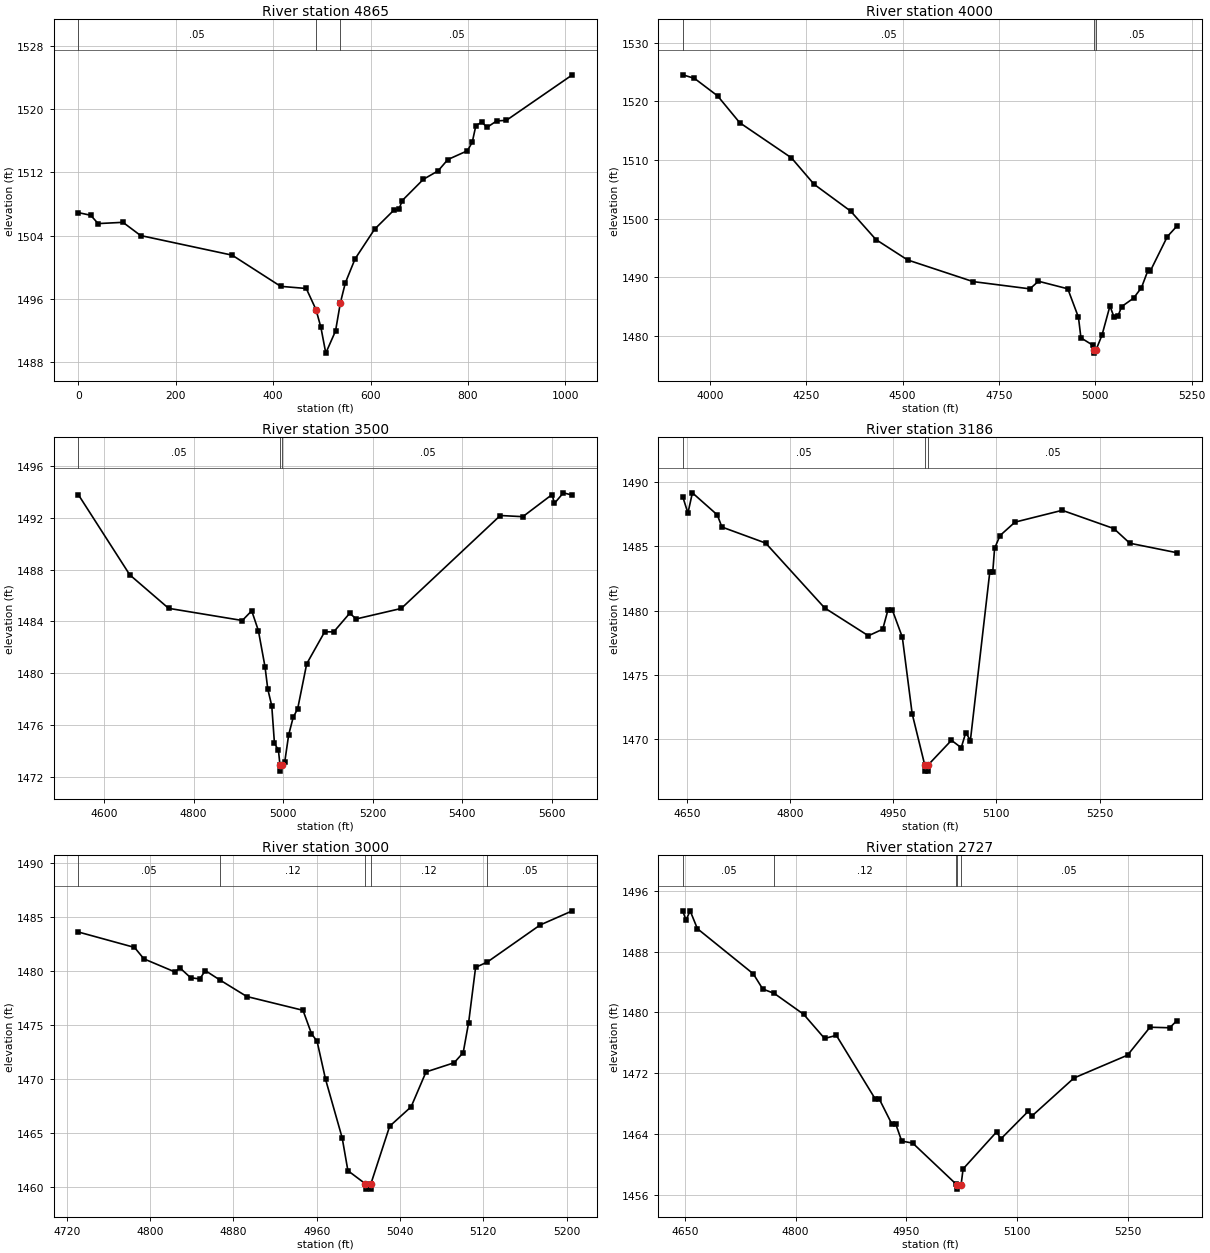
Type RM Length L Ch R = 1 ,4865    ,865,865,865
BEGIN DESCRIPTION:
SANFERNANDO019 9.0
END DESCRIPTION:
XS GIS Cut Line= 3
      2727955.68     10301503.11      2727545.27     10301421.77
      2726950.42       10301461.
#Sta/Elev= 30
       0  1506.9    25.6 1506.56    40.8 1505.51    91.8 1505.67     128    1504
     316 1501.52   415.6 1497.58   468.1 1497.31   488.1 1494.64   498.2 1492.38
   508.2 1489.14   528.2 1491.94   538.2 1495.51   548.3 1498.01   568.3 1501.05
   608.4  1504.8   648.5 1507.24   658.5 1507.33   665.1 1508.42   708.6 1511.11
   738.7 1512.17   758.7  1513.6   798.8 1514.71   808.8 1515.78   816.3 1517.89
   828.9 1518.35   838.9 1517.66   858.9 1518.48     879 1518.56  1014.4 1524.31
#Mann= 3 , 0 , 0
       0     .05       0   488.1     .05       0   538.2     .05       0
Bank Sta=488.1,538.2
XS Rating Curve= 0 ,0
Exp/Cntr=0.3,0.1

Type RM Length L Ch R = 1 ,4000    ,500,500,500
BEGIN DESCRIPTION:
SANFERNANDO019 8.0
END DESCRIPTION:
XS GIS Cut Line= 3
      2728505.71     10301153.13      2727562.73     10300647.06
      2727355.64      10300603.1
#Sta/Elev= 30
  3929.8 1524.52  3959.9 1523.92    4020 1520.93  4077.4 1516.36  4211.6 1510.37
  4270.3 1505.87  4365.1  1501.3  4430.8 1496.45  4512.8 1492.98  4682.6 1489.29
  4830.3 1488.05  4852.3 1489.35  4928.5 1488.06  4956.2  1483.2  4962.6  1479.7
  4994.4 1478.41  4996.2  1477.6  4996.6  1477.1  5001.5  1477.6  5017.4  1480.2
  5037.9 1485.14  5048.1 1483.29  5058.3 1483.37  5068.5 1485.04  5099.2 1486.47
  5119.7 1488.26  5137.2 1491.33  5142.3 1491.05  5186.8 1496.96  5211.7 1498.75
#Mann= 3 ,-1 , 0
  3929.8     .05       0  4996.2     .03       0  5001.5     .05       0
Bank Sta=4996.2,5001.5
XS Rating Curve= 0 ,0
Exp/Cntr=0.3,0.1

Type RM Length L Ch R = 1 ,3500    ,314,314,314
BEGIN DESCRIPTION:
SANFERNANDO019 7.0
END DESCRIPTION:
XS GIS Cut Line= 3
      2728155.68      10300703.1      2727897.92     10300324.64
      2727255.69     10300253.11
#Sta/Elev= 30
  4542.1 1493.79  4657.3 1487.59    4744 1485.01  4908.7 1484.07  4929.7 1484.82
  4944.6 1483.29  4959.5 1480.49  4965.6 1478.78  4974.5 1477.49  4980.5  1474.6
  4989.4 1474.06  4992.8 1472.95  4993.2 1472.45  4998.1 1472.95  5003.6 1473.18
  5012.3 1475.25  5022.4  1476.6  5032.4 1477.26  5052.6 1480.73  5092.8  1483.2
  5112.9 1483.19  5148.7 1484.63  5163.2 1484.19  5263.9    1485  5485.2 1492.17
  5535.5 1492.08    5601 1493.79    5606  1493.1  5626.1 1493.92  5646.2 1493.74
#Mann= 3 ,-1 , 0
  4542.1     .05       0  4992.8     .05       0  4998.1     .05       0
Bank Sta=4992.8,4998.1
XS Rating Curve= 0 ,0
Exp/Cntr=0.3,0.1

Type RM Length L Ch R = 1 ,3186    ,186,186,186
BEGIN DESCRIPTION:
Mapping XS 539d18b3
END DESCRIPTION:
XS GIS Cut Line= 3
      2728376.89     10300472.06       2728085.2     10300128.28
      2727840.57     10300018.98
#Sta/Elev= 30
  4643.8 1488.85  4651.2 1487.59  4657.7 1489.17    4694 1487.45  4700.6 1486.51
  4764.3 1485.26    4850 1480.22  4913.7 1478.05  4934.6 1478.56  4942.3 1480.08
  4948.8 1480.02  4963.1 1477.94  4977.4 1471.99  4995.6 1468.02    4996 1467.52
  5000.6 1467.52    5001 1468.02  5034.6 1469.92  5048.8 1469.34  5055.4 1470.52
  5062.1  1469.9  5090.4 1483.04  5094.7 1483.04  5097.3 1484.84  5105.1 1485.84
    5127 1486.89  5195.7 1487.81  5270.8 1486.39    5294 1485.25  5362.6 1484.51
#Mann= 3 ,-1 , 0
  4643.8     .05       0  4995.6     .05       0    5001     .05       0
Bank Sta=4995.6,5001
XS Rating Curve= 0 ,0
Exp/Cntr=0.3,0.1

Type RM Length L Ch R = 1 ,3000    ,273,273,273
BEGIN DESCRIPTION:
SANFERNANDO019 6.0
END DESCRIPTION:
XS GIS Cut Line= 3
       2728405.7     10300353.14      2728304.83     10300103.88
       2728105.7     10300053.12
#Sta/Elev= 30
  4731.1 1483.64  4785.1 1482.21  4794.1 1481.15  4823.6 1479.95    4829 1480.29
    4839  1479.4  4847.8 1479.29  4853.1 1480.06  4866.8 1479.21  4892.9 1477.66
  4946.9 1476.38    4955 1474.22  4960.4 1473.51  4968.5    1470  4984.5 1464.56
    4990 1461.52  5006.7 1460.31  5007.1 1459.81  5011.7 1459.81  5012.1 1460.31
  5030.1 1465.64  5050.7 1467.44    5065 1470.67    5092 1471.52  5100.7 1472.46
  5105.9 1475.24  5112.6 1480.36  5123.8 1480.85  5174.6 1484.29  5205.5  1485.6
#Mann= 5 ,-1 , 0
  4731.1     .05       0  4866.8     .12       0  5006.7     .07       0
  5012.1     .12       0  5123.8     .05       0
Bank Sta=5006.7,5012.1
XS Rating Curve= 0 ,0
Exp/Cntr=0.3,0.1

Type RM Length L Ch R = 1 ,2727    ,227,227,227
BEGIN DESCRIPTION:
Mapping XS ca1b7b00
END DESCRIPTION:
XS GIS Cut Line= 3
      2728793.49     10300060.55       2728397.7     10299873.07
      2728169.62     10299836.79
#Sta/Elev= 30
  4647.4  1493.3  4651.8 1492.18  4657.3 1493.38  4667.1 1491.03  4742.8 1485.08
  4755.6 1483.08  4771.1 1482.51    4811 1479.75  4839.3 1476.57  4855.2 1476.98
  4907.5 1468.66  4913.1 1468.64  4930.3 1465.31  4935.8 1465.25  4943.7 1463.06
  4958.6 1462.79  5017.1 1457.41  5018.4 1457.23  5018.8 1456.73    5024 1457.23
  5026.8 1459.39  5072.3 1464.28  5077.8 1463.33  5114.8 1466.96  5119.9 1466.35
    5177 1471.37  5249.4 1474.37  5279.8 1478.05  5306.5 1477.98  5316.3 1478.93
#Mann= 5 ,-1 , 0
  4647.4     .05       0  4771.1     .12       0  5017.1     .05       0
  5018.4     .07       0    5024     .05       0
Bank Sta=5018.4,5024
XS Rating Curve= 0 ,0
Exp/Cntr=0.3,0.1

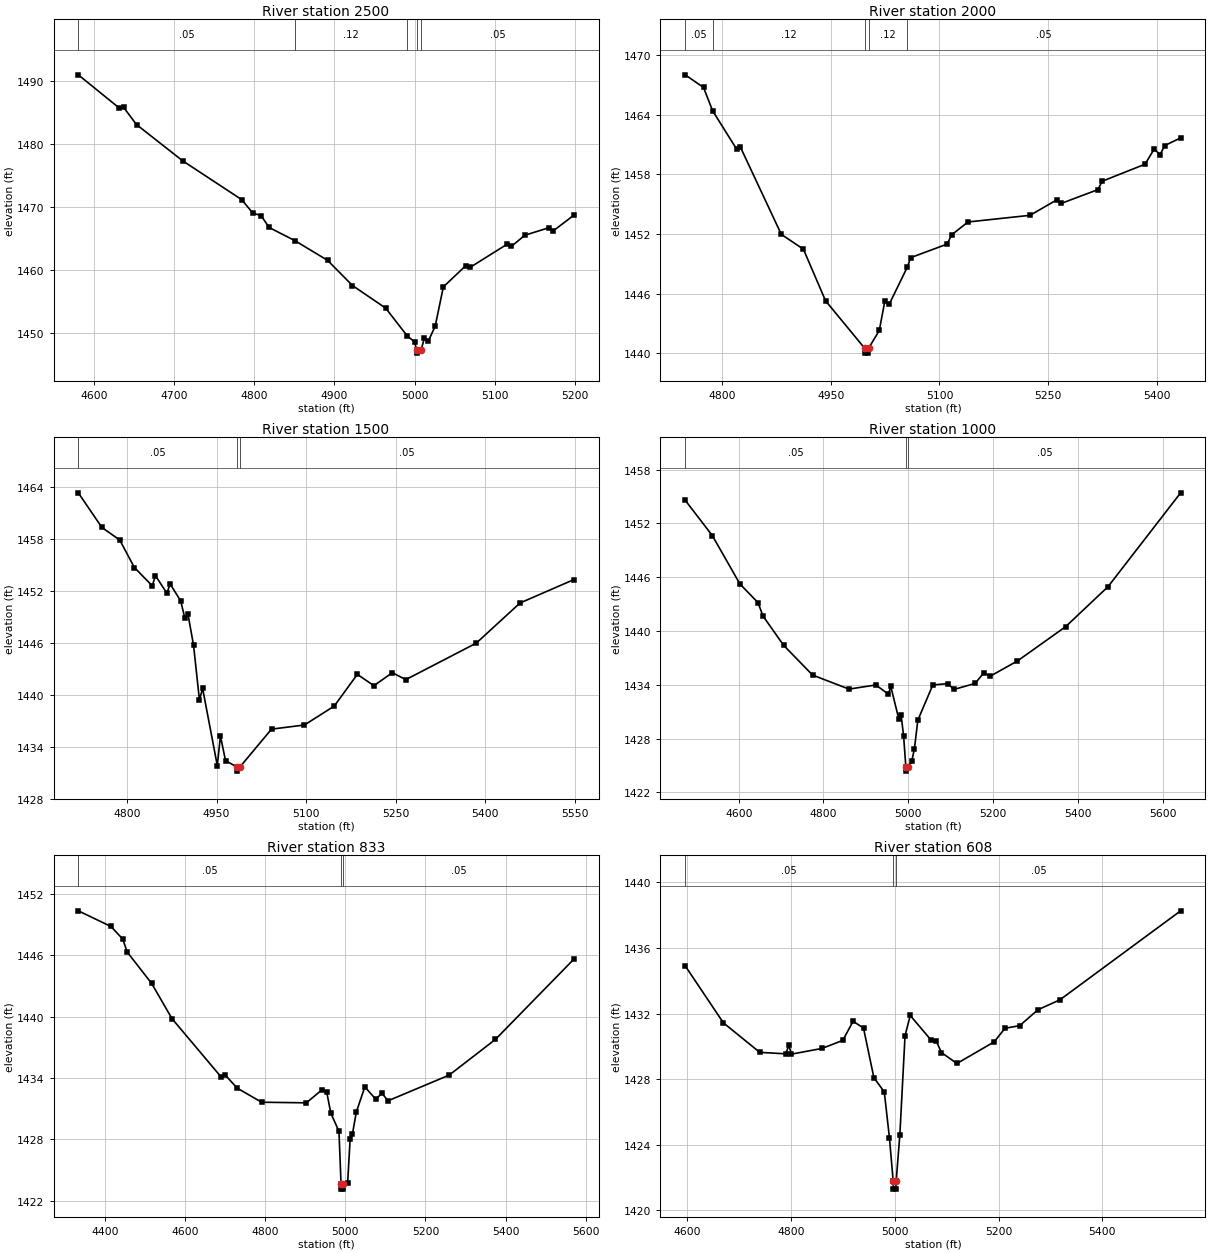
Type RM Length L Ch R = 1 ,2500    ,500,500,500
BEGIN DESCRIPTION:
SANFERNANDO019 5.0
END DESCRIPTION:
XS GIS Cut Line= 3
      2728855.72     10299803.12      2728451.03     10299690.76
      2728255.72     10299653.12
#Sta/Elev= 30
    4580 1490.93  4631.4 1485.64  4636.6 1485.77  4652.7 1483.04  4710.3  1477.3
    4784 1471.15    4798 1469.01  4808.4  1468.6  4818.3 1466.73  4850.6 1464.63
  4891.4 1461.51  4922.5 1457.52    4964 1453.93  4990.9 1449.53    5000 1448.59
  5002.6  1447.3  5003.1  1446.8  5008.2  1447.3  5012.3 1449.17  5017.4 1448.76
  5025.8 1451.06    5036  1457.3  5064.1 1460.68  5069.2 1460.38    5116  1464.1
  5121.1 1463.74  5137.8 1465.49  5167.9 1466.69    5173 1466.15  5198.9 1468.66
#Mann= 5 ,-1 , 0
    4580     .05       0  4850.6     .12       0  4990.9     .05       0
  5002.6     .03       0  5008.2     .05       0
Bank Sta=5002.6,5008.2
XS Rating Curve= 0 ,0
Exp/Cntr=0.3,0.1

Type RM Length L Ch R = 1 ,2000    ,500,500,500
BEGIN DESCRIPTION:
SANFERNANDO019 4.0
END DESCRIPTION:
XS GIS Cut Line= 3
      2728755.68     10299153.11      2728509.51      10299203.1
      2728155.72     10299453.09
#Sta/Elev= 30
  4748.8 1468.02  4774.1 1466.75  4786.6 1464.41  4819.7 1460.56  4824.8 1460.79
  4881.5 1451.98  4912.1 1450.48  4942.7 1445.29  4996.6 1440.53    4997 1440.03
  5001.7 1440.03  5002.2 1440.53  5016.9 1442.31  5024.5 1445.24  5030.7 1444.96
  5055.8 1448.71  5060.2 1449.63  5110.7    1451  5116.8 1451.92  5139.4 1453.22
  5225.1 1453.89  5261.8 1455.43  5268.3 1455.09  5318.8 1456.47  5324.9 1457.32
    5384 1459.03  5396.5 1460.54  5404.9    1460  5411.1  1460.9  5433.2 1461.68
#Mann= 5 ,-1 , 0
  4748.8     .05       0  4786.6     .12       0  4996.6     .07       0
  5002.2     .12       0  5055.8     .05       0
Bank Sta=4996.6,5002.2
XS Rating Curve= 0 ,0
Exp/Cntr=0.3,0.1

Type RM Length L Ch R = 1 ,1500    ,500,500,500
BEGIN DESCRIPTION:
SANFERNANDO019 3.0
END DESCRIPTION:
XS GIS Cut Line= 3
      2728605.69     10298853.11      2728343.03      10298751.3
      2727855.65     10299003.13
#Sta/Elev= 30
  4718.3 1463.36  4757.8 1459.36  4787.7 1457.91  4812.3 1454.73  4842.2 1452.62
  4847.6 1453.79  4866.8 1451.76  4872.1 1452.84  4889.9 1450.87  4896.7 1448.92
  4902.1 1449.33  4911.4 1445.76  4921.3 1439.43  4926.6 1440.77  4951.2 1431.86
  4956.5 1435.27    4965 1432.42  4983.6 1431.71  4984.1 1431.21  4989.4 1431.71
  5042.1 1436.06  5097.3 1436.54  5147.3 1438.73  5185.9 1442.39  5213.7 1441.08
  5244.6 1442.58  5267.2 1441.78  5385.3    1446  5458.5 1450.63  5548.6 1453.33
#Mann= 3 ,-1 , 0
  4718.3     .05       0  4983.6     .05       0  4989.4     .05       0
Bank Sta=4983.6,4989.4
XS Rating Curve= 0 ,0
Exp/Cntr=0.3,0.1

Type RM Length L Ch R = 1 ,1000    ,167,167,167
BEGIN DESCRIPTION:
SANFERNANDO019 2.0
END DESCRIPTION:
XS GIS Cut Line= 3
      2728605.73     10298503.13      2728115.52     10298311.86
      2727605.65     10298703.14
#Sta/Elev= 30
  4473.8 1454.58  4537.8 1450.64  4602.8 1445.25  4645.6 1443.16  4657.2 1441.68
  4706.2 1438.39  4774.4 1435.08  4860.3 1433.52  4923.5 1433.98  4953.4 1432.95
  4958.8 1433.82  4977.9 1430.15  4983.3 1430.58  4989.1 1428.28  4994.3 1424.87
  4994.8 1424.37  5000.1 1424.87  5008.2 1425.45  5014.5 1426.85  5022.7 1430.06
    5058 1433.98  5093.4 1434.13  5107.9 1433.48  5157.7 1434.15  5178.5 1435.34
  5193.1 1434.95  5257.4 1436.65  5371.6 1440.49  5471.3 1444.94  5642.7 1455.41
#Mann= 3 ,-1 , 0
  4473.8     .05       0  4994.3     .05       0  5000.1     .05       0
Bank Sta=4994.3,5000.1
XS Rating Curve= 0 ,0
Exp/Cntr=0.3,0.1

Type RM Length L Ch R = 1 ,833     ,225,225,225
BEGIN DESCRIPTION:
Mapping XS a2695bd4
END DESCRIPTION:
XS GIS Cut Line= 3
       2728725.8      10298268.9      2728074.78     10298149.11
      2727585.22     10298451.18
#Sta/Elev= 30
  4333.2 1450.36  4414.7 1448.83  4444.1  1447.6  4455.3 1446.33  4516.3 1443.26
  4567.2 1439.81  4689.2 1434.14  4699.4 1434.33  4729.9 1433.02  4790.9 1431.64
  4902.7 1431.58  4941.9 1432.86  4953.6 1432.62  4963.7 1430.58  4984.1 1428.79
  4989.3 1423.64  4989.7 1423.14  4994.6 1423.14  4995.1 1423.64  5005.8 1423.78
    5012 1428.03  5017.9 1428.56  5027.4 1430.67  5048.7 1433.14  5076.3 1431.92
  5091.2 1432.53  5106.6 1431.78  5259.2 1434.29    5375 1437.79  5570.4 1445.62
#Mann= 3 ,-1 , 0
  4333.2     .05       0  4989.3     .05       0  4995.1     .05       0
Bank Sta=4989.3,4995.1
XS Rating Curve= 0 ,0
Exp/Cntr=0.3,0.1

Type RM Length L Ch R = 1 ,608     ,253,253,253
BEGIN DESCRIPTION:
Mapping XS 1ad1ebe0
END DESCRIPTION:
XS GIS Cut Line= 3
      2728439.34     10297945.99      2727908.11     10297925.15
      2727621.63     10298237.68
#Sta/Elev= 30
  4595.6 1434.91  4669.3 1431.43  4739.4 1429.63  4789.4 1429.54  4795.5 1430.05
  4800.5 1429.52  4859.5 1429.87  4899.5 1430.36  4919.5 1431.53  4939.5 1431.11
  4959.5 1428.09  4979.6 1427.21  4989.6 1424.39  4996.7 1421.78  4997.1 1421.28
    5002 1421.28  5002.5 1421.78  5009.6 1424.59  5019.6 1430.64  5029.6 1431.88
  5069.6 1430.39  5079.6 1430.35  5089.6 1429.62  5119.7 1428.95  5191.5 1430.27
  5212.4  1431.1  5240.8 1431.26  5275.9 1432.23  5318.5 1432.84  5551.2 1438.27
#Mann= 3 ,-1 , 0
  4595.6     .05       0  4996.7     .03       0  5002.5     .05       0
Bank Sta=4996.7,5002.5
XS Rating Curve= 0 ,0
Exp/Cntr=0.3,0.1

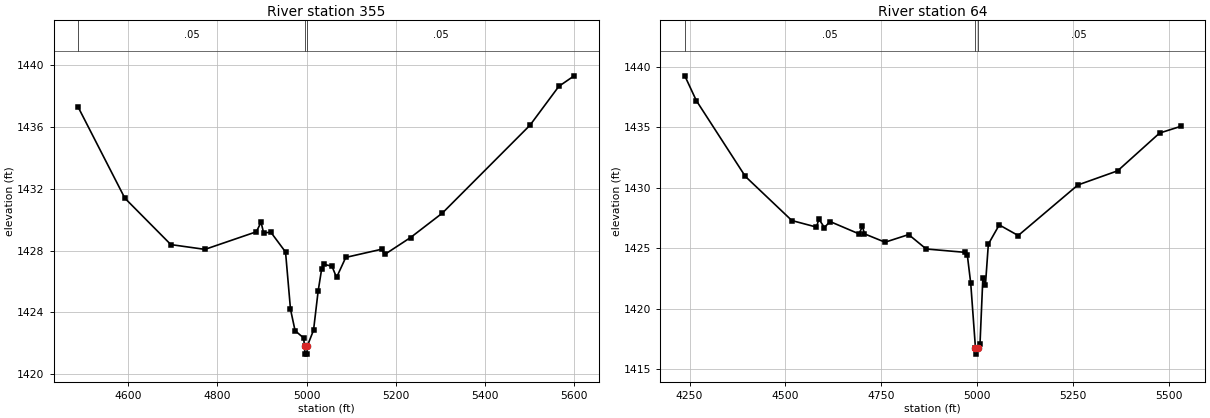
Type RM Length L Ch R = 1 ,355     ,291,291,291
BEGIN DESCRIPTION:
Mapping XS 74bcc086
END DESCRIPTION:
XS GIS Cut Line= 5
      2728487.64     10297883.83      2728093.08     10297672.69
      2727888.34     10297726.01      2727709.19     10297856.11
      2727510.84     10297975.54
#Sta/Elev= 30
    4488 1437.28  4592.3  1431.4  4695.5 1428.39  4771.9 1428.08  4887.2 1429.22
  4897.8 1429.84  4903.5 1429.15  4919.8 1429.19  4952.7 1427.91  4963.8  1424.2
  4974.1 1422.81  4993.2 1422.34  4995.4 1421.79  4995.9 1421.29  5000.8 1421.29
  5001.2 1421.79  5015.5 1422.84  5025.8 1425.37  5033.7 1426.81  5038.8 1427.11
  5056.8 1426.99  5067.1 1426.26  5087.8 1427.56  5168.3 1428.09  5175.1 1427.75
  5233.2 1428.85  5304.3 1430.43    5501 1436.13  5565.7 1438.65    5600 1439.33
#Mann= 3 ,-1 , 0
    4488     .05       0  4995.4     .03       0  5001.2     .05       0
Bank Sta=4995.4,5001.2
XS Rating Curve= 0 ,0
Exp/Cntr=0.3,0.1

Type RM Length L Ch R = 1 ,64      ,0,0,0
BEGIN DESCRIPTION:
SANFERNANDO019 1.0
END DESCRIPTION:
XS GIS Cut Line= 5
      2728523.88     10297866.75      2728275.67     10297553.16
      2727939.75       10297417.      2727736.92     10297595.92
      2727613.23     10297823.85
#Sta/Elev= 30
  4237.6 1439.24  4267.7 1437.19  4395.3 1430.93  4516.6 1427.28  4580.7 1426.74
    4587  1427.4  4601.5  1426.7  4615.9  1427.2  4691.5 1426.18  4700.5 1426.79
  4705.9 1426.18  4759.5 1425.49    4821 1426.12  4866.7 1424.93  4968.5 1424.65
  4973.9 1424.43  4982.8 1422.09  4995.1 1416.74  4995.6 1416.24    5001 1416.74
  5006.9 1417.05  5014.4 1422.55  5021.1 1421.95  5028.7 1425.33  5057.1 1426.92
  5106.5 1426.04  5262.1 1430.22  5365.7 1431.39    5475 1434.51  5529.8 1435.06
#Mann= 3 ,-1 , 0
  4237.6     .05       0  4995.1     .03       0    5001     .05       0
Bank Sta=4995.1,5001
XS Rating Curve= 0 ,0
Exp/Cntr=0.3,0.1
Stream Node=SANFERNANDO019  ,Reach-1         , 0 , 0 ,Upstream end
Stream Node=SANFERNANDO019  ,Reach-1         , 0 , 1 ,Downstream end

Chan Stop Cuts=-1
Use User Specified Reach Order=0
Composite Channel Slope=5