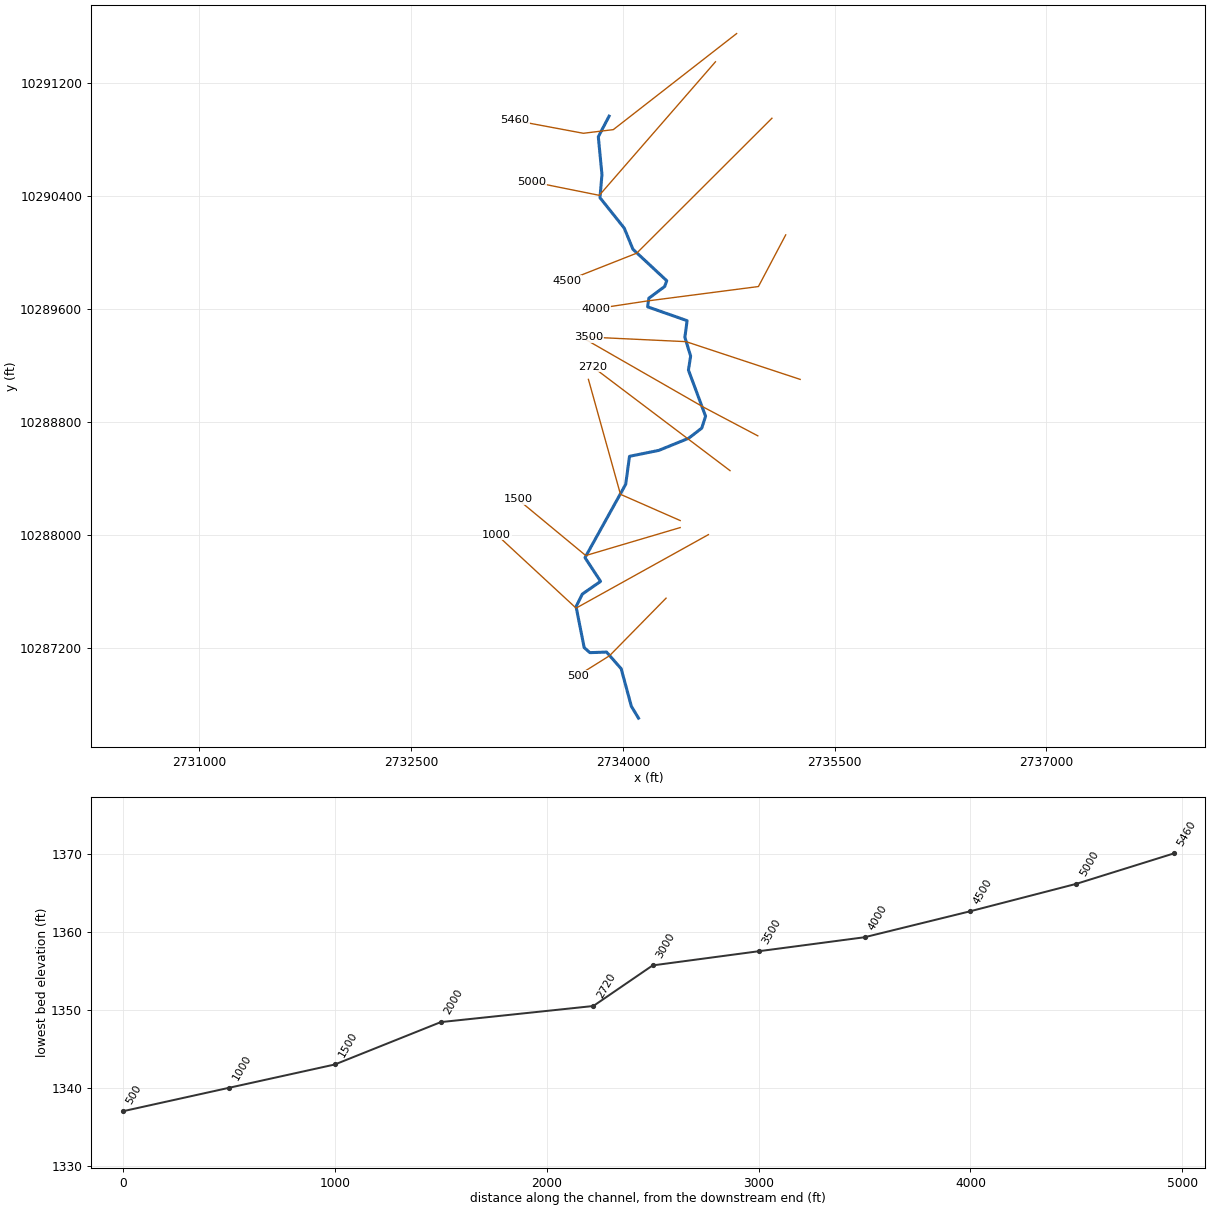
--- SANFERNANDO021.prj (project) ---

Proj Title=SANFERNANDO021 Base Level Engineering
Current Plan=p01
Default Exp/Contr=0.3,0.1
English Units
Geom File=g01
Flow File=f01
Plan File=p01
BEGIN DESCRIPTION:
SANFERNANDO021
END DESCRIPTION:

--- SANFERNANDO021.p01 (plan) ---

Plan Title=Multiple Run
Short Identifier=Multiple
Geom File=g01
Flow File=f01
Subcritical Flow
K Sum by GR= 0
Std Step Tol= 0.01
Critical Tol= 0.01
Num of Std Step Trials= 20
Max Error Tol= 0.3
Flow Tol Ratio= 0.001
Split Flow NTrial= 30
Split Flow Tol= 0.02
Split Flow Ratio= 0.02
Log Output Level= 0
Friction Slope Method= 1
Unsteady Friction Slope Method= 2
Unsteady Bridges Friction Slope Method= 1
Parabolic Critical Depth
Global Vel Dist=  1 , 1 , 1
Global Log Level= 0
CheckData=True
Encroach Param= -1, 0, 0, 0
BEGIN DESCRIPTION:
Multiple Run
END DESCRIPTION:

--- SANFERNANDO021.f01 (steady flow) ---

Flow Title=Multiple
Number of Profiles=7
Profile Names=10-year,25-year,50-year,1pct_min,100-year,1pct_plu,500-year
River Rch & RM= SANFERNANDO021,Reach-1,5460
     445     720    1492     913    2098    4820    3046
River Rch & RM= SANFERNANDO021,Reach-1,3000
     550     908    1728    1238    2428    4763    3504
Boundary for River Rch & Prof#=SANFERNANDO021,Reach-1,1
Up Type=0
Dn Type=3
Dn Slope=0.005
Boundary for River Rch & Prof#=SANFERNANDO021,Reach-1,2
Up Type=0
Dn Type=3
Dn Slope=0.005
Boundary for River Rch & Prof#=SANFERNANDO021,Reach-1,3
Up Type=0
Dn Type=3
Dn Slope=0.005
Boundary for River Rch & Prof#=SANFERNANDO021,Reach-1,4
Up Type=0
Dn Type=3
Dn Slope=0.005
Boundary for River Rch & Prof#=SANFERNANDO021,Reach-1,5
Up Type=0
Dn Type=3
Dn Slope=0.005
Boundary for River Rch & Prof#=SANFERNANDO021,Reach-1,6
Up Type=0
Dn Type=3
Dn Slope=0.005
Boundary for River Rch & Prof#=SANFERNANDO021,Reach-1,7
Up Type=0
Dn Type=3
Dn Slope=0.005

--- SANFERNANDO021.g01 (geometry) ---

Geom Title=Existing Conditions

River Reach=SANFERNANDO021,Reach-1
Reach XY= 30
      2733902.25     10290968.00      2733825.75     10290822.00
      2733851.50     10290554.00      2733837.50     10290390.00
      2734009.25     10290175.00      2734071.00     10290025.00
      2734310.50     10289802.00      2734295.75     10289761.00
      2734183.75     10289678.00      2734175.00     10289617.00
      2734454.75     10289519.00      2734439.00     10289401.00
      2734479.75     10289268.00      2734464.25     10289169.00
      2734585.75     10288842.00      2734558.75     10288758.00
      2734466.00     10288686.00      2734254.25     10288600.00
      2734046.75     10288558.00      2734019.75     10288360.00
      2733731.50     10287840.00      2733841.75     10287672.00
      2733712.50     10287582.00      2733668.25     10287493.00
      2733725.50     10287203.00      2733765.50     10287167.00
      2733884.25     10287171.00      2733987.75     10287053.00
      2734059.75     10286787.00      2734110.50     10286703.00

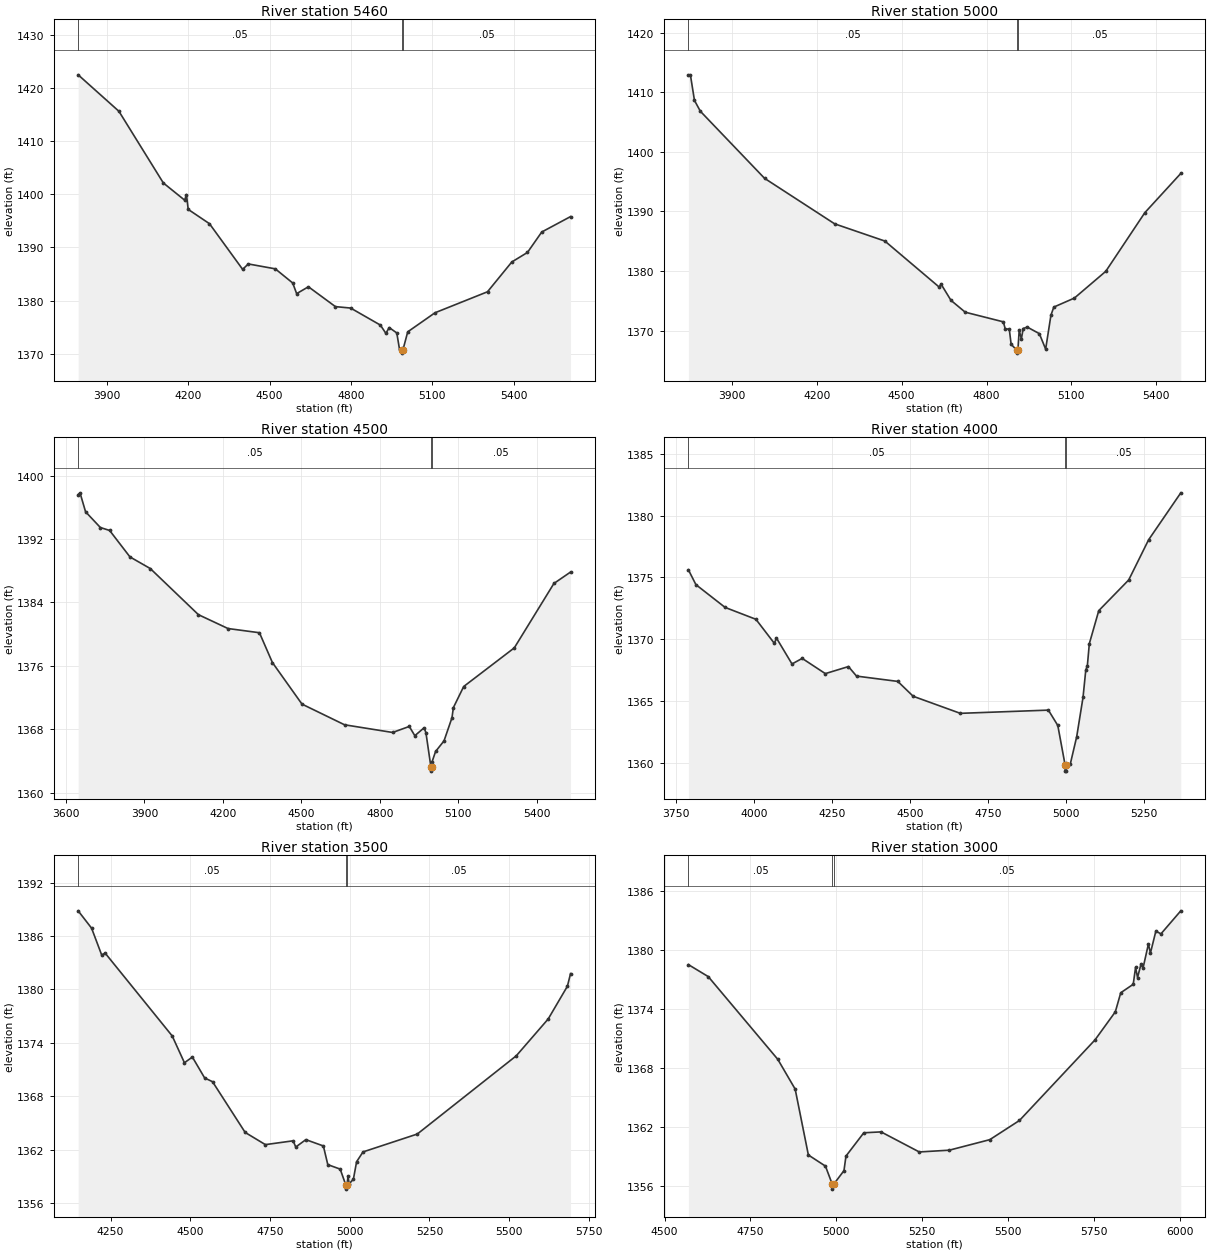
Type RM Length L Ch R = 1,5460,460,460,460
BEGIN DESCRIPTION:
SANFERNANDO021 11.0
END DESCRIPTION:
XS GIS Cut Line= 4
      2734805.67     10291553.10      2733931.95     10290872.51
      2733719.59     10290846.60      2733234.76     10290937.37
#Sta/Elev= 30
  3794.5 1422.43  3944.7 1415.58  4108.4 1402.11  4187.1 1398.87  4193.5 1399.93
  4200.1 1397.14  4278.5 1394.45  4400.7 1385.87  4421.5 1386.89  4521.0 1385.97
  4585.2 1383.31  4599.7 1381.31  4643.1 1382.60  4742.6 1378.87  4798.7 1378.60
  4908.3 1375.40  4928.5 1373.85  4941.0 1374.93  4968.8 1373.92  4978.8 1370.86
  4986.9 1370.63  4987.2 1370.13  4990.9 1370.63  5009.1 1374.13  5109.8 1377.72
  5303.1 1381.66  5392.7 1387.26  5450.4 1389.05  5503.0 1392.89  5609.2 1395.79
#Mann=3,-1,0
  3794.5    0.05       0  4986.9    0.05       0  4990.9    0.05       0
Bank Sta=4986.9,4990.9
Exp/Cntr=0.3,0.1

Type RM Length L Ch R = 1,5000,500,500,500
BEGIN DESCRIPTION:
SANFERNANDO021 10.0
END DESCRIPTION:
XS GIS Cut Line= 3
      2734655.67     10291353.10      2733832.74     10290407.03
      2733355.72     10290503.10
#Sta/Elev= 30
  3746.1 1412.93  3753.2 1412.92  3767.5 1408.64  3788.3 1406.82  4015.3 1395.56
  4263.1 1387.92  4440.6 1385.03  4632.5 1377.31  4639.1 1377.81  4674.2 1375.08
  4724.6 1373.09  4859.4 1371.47  4866.0 1370.29  4880.3 1370.25  4886.9 1367.70
  4906.8 1366.72  4907.0 1366.22  4910.8 1366.72  4915.4 1370.08  4923.0 1368.59
  4929.6 1370.35  4943.9 1370.59  4986.6 1369.49  5008.9 1366.89  5027.6 1372.59
  5037.8 1373.95  5110.5 1375.46  5221.4 1379.95  5359.6 1389.80  5486.6 1396.38
#Mann=3,-1,0
  3746.1    0.05       0  4906.8    0.05       0  4910.8    0.05       0
Bank Sta=4906.8,4910.8
Exp/Cntr=0.3,0.1

Type RM Length L Ch R = 1,4500,500,500,500
BEGIN DESCRIPTION:
SANFERNANDO021 9.0
END DESCRIPTION:
XS GIS Cut Line= 3
      2735055.72     10290953.14      2734097.80     10289997.21
      2733605.69     10289803.11
#Sta/Elev= 30
  3646.7 1397.61  3653.8 1397.83  3675.0 1395.44  3731.6 1393.45  3767.0 1393.08
  3844.7 1389.74  3922.5 1388.27  4106.4 1382.45  4219.5 1380.70  4339.7 1380.17
  4389.2 1376.41  4502.3 1371.16  4665.0 1368.55  4848.8 1367.58  4912.5 1368.34
  4933.7 1367.17  4969.0 1368.17  4976.1 1367.56  4995.3 1363.20  4995.6 1362.70
  4999.3 1363.20  4999.4 1363.86  5013.0 1365.18  5045.3 1366.52  5075.7 1369.44
  5081.1 1370.72  5120.5 1373.38  5314.0 1378.26  5465.4 1386.39  5529.0 1387.83
#Mann=3,-1,0
  3646.7    0.05       0  4995.3    0.05       0  4999.3    0.05       0
Bank Sta=4995.3,4999.3
Exp/Cntr=0.3,0.1

Type RM Length L Ch R = 1,4000,500,500,500
BEGIN DESCRIPTION:
SANFERNANDO021 8.0
END DESCRIPTION:
XS GIS Cut Line= 4
      2735153.37     10290126.64      2734960.01     10289760.82
      2734170.32     10289658.26      2733805.67     10289603.11
#Sta/Elev= 30
  3789.9 1375.62  3814.0 1374.42  3907.6 1372.58  4006.4 1371.62  4065.4 1369.68
  4072.4 1370.10  4122.1 1368.01  4154.8 1368.46  4229.0 1367.23  4303.1 1367.80
  4329.0 1367.03  4461.4 1366.60  4510.6 1365.40  4661.8 1364.02  4944.2 1364.28
  4974.4 1363.04  4997.8 1359.85  4998.1 1359.35  5001.6 1359.35  5001.8 1359.85
  5014.8 1359.96  5035.0 1362.13  5055.3 1365.31  5064.1 1367.51  5069.2 1367.87
  5075.5 1369.65  5105.8 1372.32  5201.8 1374.80  5265.5 1378.04  5368.8 1381.84
#Mann=3,-1,0
  3789.9    0.05       0  4997.8    0.05       0  5001.8    0.05       0
Bank Sta=4997.8,5001.8
Exp/Cntr=0.3,0.1

Type RM Length L Ch R = 1,3500,500,500,500
BEGIN DESCRIPTION:
SANFERNANDO021 7.0
END DESCRIPTION:
XS GIS Cut Line= 3
      2735255.69     10289103.11      2734447.21     10289370.33
      2733755.68     10289403.11
#Sta/Elev= 30
  4148.5 1388.82  4190.6 1386.87  4222.2 1383.86  4233.1 1384.07  4443.4 1374.76
  4481.7 1371.75  4506.6 1372.39  4545.1 1370.04  4569.8 1369.62  4672.1 1363.92
  4735.5 1362.55  4822.6 1362.98  4830.7 1362.28  4862.4 1363.11  4917.3 1362.40
  4931.2 1360.30  4970.0 1359.80  4987.3 1358.05  4987.5 1357.55  4991.5 1358.05
  4994.6 1359.00  4998.2 1358.14  5011.5 1358.68  5021.5 1360.63  5041.6 1361.73
  5211.8 1363.74  5522.1 1372.53  5622.2 1376.67  5682.3 1380.34  5692.3 1381.77
#Mann=3,-1,0
  4148.5    0.05       0  4987.3    0.03       0  4991.5    0.05       0
Bank Sta=4987.3,4991.5
Exp/Cntr=0.3,0.1

Type RM Length L Ch R = 1,3000,280,280,280
BEGIN DESCRIPTION:
SANFERNANDO021 6.0
END DESCRIPTION:
XS GIS Cut Line= 3
      2734955.65     10288703.13      2734574.96     10288904.16
      2733705.68     10289403.11
#Sta/Elev= 30
  4569.5 1378.56  4627.3 1377.34  4829.6 1368.93  4880.2 1365.90  4918.6 1359.20
  4968.3 1358.07  4988.1 1356.23  4988.4 1355.73  4992.4 1356.23  5022.2 1357.61
  5028.0 1359.09  5079.9 1361.46  5130.1 1361.55  5241.3 1359.51  5328.6 1359.69
  5446.5 1360.76  5532.8 1362.71  5752.8 1370.91  5811.8 1373.76  5827.6 1375.70
  5863.9 1376.56  5870.7 1378.28  5876.5 1377.25  5886.5 1378.61  5892.3 1378.19
  5908.1 1380.66  5913.9 1379.73  5929.7 1381.96  5944.6 1381.69  6002.3 1384.03
#Mann=3,-1,0
  4569.5    0.05       0  4988.1    0.05       0  4992.4    0.05       0
Bank Sta=4988.1,4992.4
Exp/Cntr=0.3,0.1

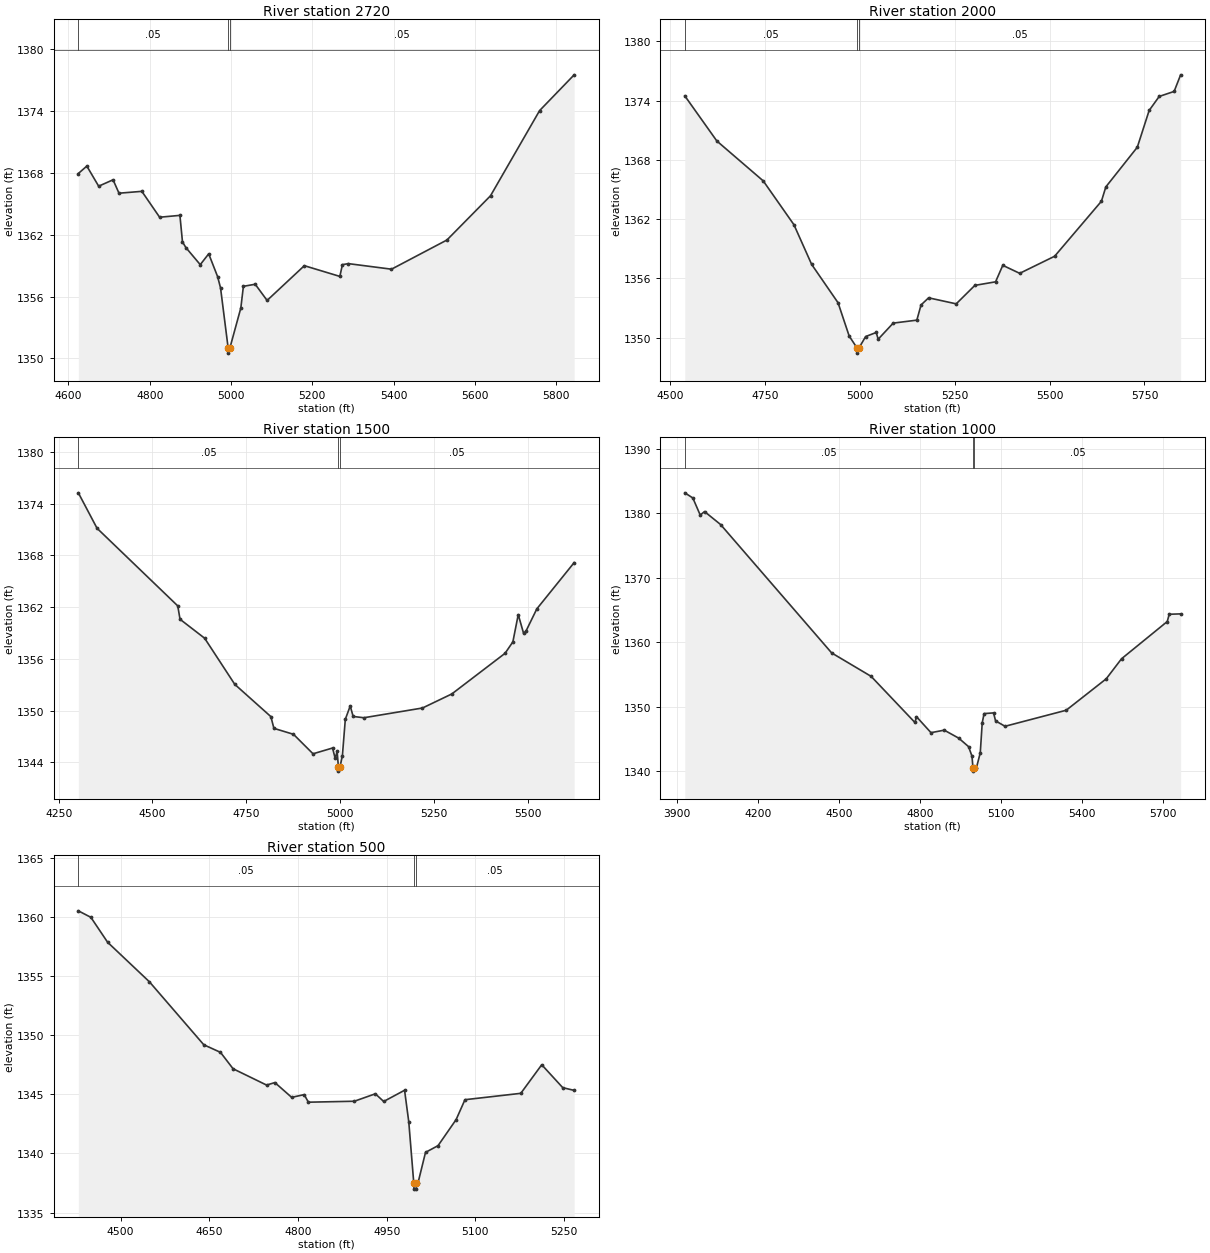
Type RM Length L Ch R = 1,2720,720,720,720
BEGIN DESCRIPTION:
Mapping XS bbfb6b70
END DESCRIPTION:
XS GIS Cut Line= 2
      2734758.85     10288456.66      2733786.01     10289191.69
#Sta/Elev= 30
  4624.5 1367.93  4645.4 1368.65  4674.5 1366.70  4709.9 1367.32  4724.5 1366.02
  4780.7 1366.20  4824.4 1363.69  4874.3 1363.87  4880.6 1361.30  4888.9 1360.75
  4924.3 1359.09  4945.1 1360.14  4966.9 1357.94  4974.2 1356.84  4992.9 1351.01
  4993.2 1350.51  4997.2 1351.01  5024.1 1354.89  5030.4 1356.99  5059.5 1357.19
  5088.7 1355.62  5180.3 1358.99  5267.6 1357.95  5273.9 1359.09  5288.5 1359.19
  5394.6 1358.65  5530.9 1361.48  5638.1 1365.77  5758.8 1374.03  5843.8 1377.50
#Mann=3,-1,0
  4624.5    0.05       0  4992.9    0.03       0  4997.2    0.05       0
Bank Sta=4992.9,4997.2
Exp/Cntr=0.3,0.1

Type RM Length L Ch R = 1,2000,500,500,500
BEGIN DESCRIPTION:
SANFERNANDO021 4.0
END DESCRIPTION:
XS GIS Cut Line= 3
      2734405.68     10288103.11      2733982.73     10288288.76
      2733755.69     10289103.11
#Sta/Elev= 30
  4538.1 1374.49  4622.6 1369.92  4744.9 1365.88  4825.9 1361.44  4872.6 1357.42
  4942.2 1353.54  4971.5 1350.17  4992.6 1348.94  4992.9 1348.44  4997.0 1348.94
  5014.9 1350.12  5042.8 1350.53  5048.0 1349.85  5087.6 1351.48  5149.9 1351.78
  5161.0 1353.32  5181.0 1354.04  5253.7 1353.43  5302.9 1355.30  5357.5 1355.66
  5376.5 1357.33  5421.1 1356.52  5513.2 1358.25  5636.6 1363.82  5648.2 1365.27
  5731.2 1369.29  5762.4 1373.01  5788.9 1374.43  5828.3 1374.94  5845.4 1376.62
#Mann=3,-1,0
  4538.1    0.05       0  4992.6    0.04       0  4997.0    0.05       0
Bank Sta=4992.6,4997
Exp/Cntr=0.3,0.1

Type RM Length L Ch R = 1,1500,500,500,500
BEGIN DESCRIPTION:
SANFERNANDO021 3.0
END DESCRIPTION:
XS GIS Cut Line= 3
      2734405.71     10288053.12      2733736.74     10287854.98
      2733255.72     10288253.08
#Sta/Elev= 30
  4302.3 1375.26  4352.2 1371.15  4567.4 1362.15  4573.5 1360.60  4639.1 1358.40
  4719.5 1353.05  4815.7 1349.31  4823.8 1347.95  4876.0 1347.26  4928.1 1345.00
  4980.2 1345.67  4987.2 1344.46  4992.4 1345.29  4995.7 1343.49  4996.0 1342.99
  5000.1 1343.49  5006.4 1344.78  5014.2 1349.00  5027.3 1350.55  5035.1 1349.33
  5063.7 1349.18  5220.0 1350.31  5298.2 1351.94  5440.1 1356.65  5461.0 1357.98
  5475.3 1361.14  5489.6 1358.96  5496.1 1359.24  5524.8 1361.80  5624.4 1367.17
#Mann=3,-1,0
  4302.3    0.05       0  4995.7    0.05       0  5000.1    0.05       0
Bank Sta=4995.7,5000.1
Exp/Cntr=0.3,0.1

Type RM Length L Ch R = 1,1000,500,500,500
BEGIN DESCRIPTION:
SANFERNANDO021 2.0
END DESCRIPTION:
XS GIS Cut Line= 3
      2734605.69     10288003.11      2733668.25     10287482.50
      2733105.68     10288003.12
#Sta/Elev= 30
  3927.7 1383.19  3957.5 1382.39  3984.9 1379.74  4000.9 1380.28  4060.4 1378.27
  4472.3 1358.34  4618.7 1354.70  4781.2 1347.54  4786.9 1348.44  4840.7 1345.96
  4889.9 1346.35  4943.6 1345.11  4980.1 1343.79  4992.8 1342.30  4996.4 1340.49
  4996.7 1339.99  5000.9 1340.49  5009.3 1340.52  5023.5 1342.84  5030.7 1347.48
  5037.6 1348.92  5072.8 1349.03  5080.2 1347.79  5115.3 1346.95  5342.1 1349.44
  5490.6 1354.32  5547.3 1357.43  5716.9 1363.21  5724.2 1364.34  5766.5 1364.40
#Mann=3,-1,0
  3927.7    0.05       0  4996.4    0.05       0  5000.9    0.05       0
Bank Sta=4996.4,5000.9
Exp/Cntr=0.3,0.1

Type RM Length L Ch R = 1,500,0,0,0
BEGIN DESCRIPTION:
SANFERNANDO021 1.0
END DESCRIPTION:
XS GIS Cut Line= 3
      2734305.65     10287553.08      2733905.46     10287145.36
      2733679.29     10287003.66
#Sta/Elev= 30
  4428.7 1360.54  4449.9 1359.99  4478.2 1357.88  4548.9 1354.53  4640.8 1349.20
  4669.0 1348.56  4690.3 1347.17  4746.9 1345.79  4761.0 1346.00  4789.3 1344.75
  4810.5 1344.98  4817.6 1344.34  4895.3 1344.42  4930.8 1345.05  4944.9 1344.40
  4980.2 1345.35  4987.3 1342.68  4995.8 1337.48  4996.1 1336.98  5000.0 1336.98
  5000.3 1337.48  5002.8 1337.48  5015.6 1340.09  5036.8 1340.66  5067.4 1342.87
  5082.3 1344.55  5176.7 1345.09  5212.1 1347.51  5247.6 1345.57  5266.9 1345.34
#Mann=3,-1,0
  4428.7    0.05       0  4995.8    0.04       0  5000.3    0.05       0
Bank Sta=4995.8,5000.3
Exp/Cntr=0.3,0.1

Chan Stop Cuts=-1