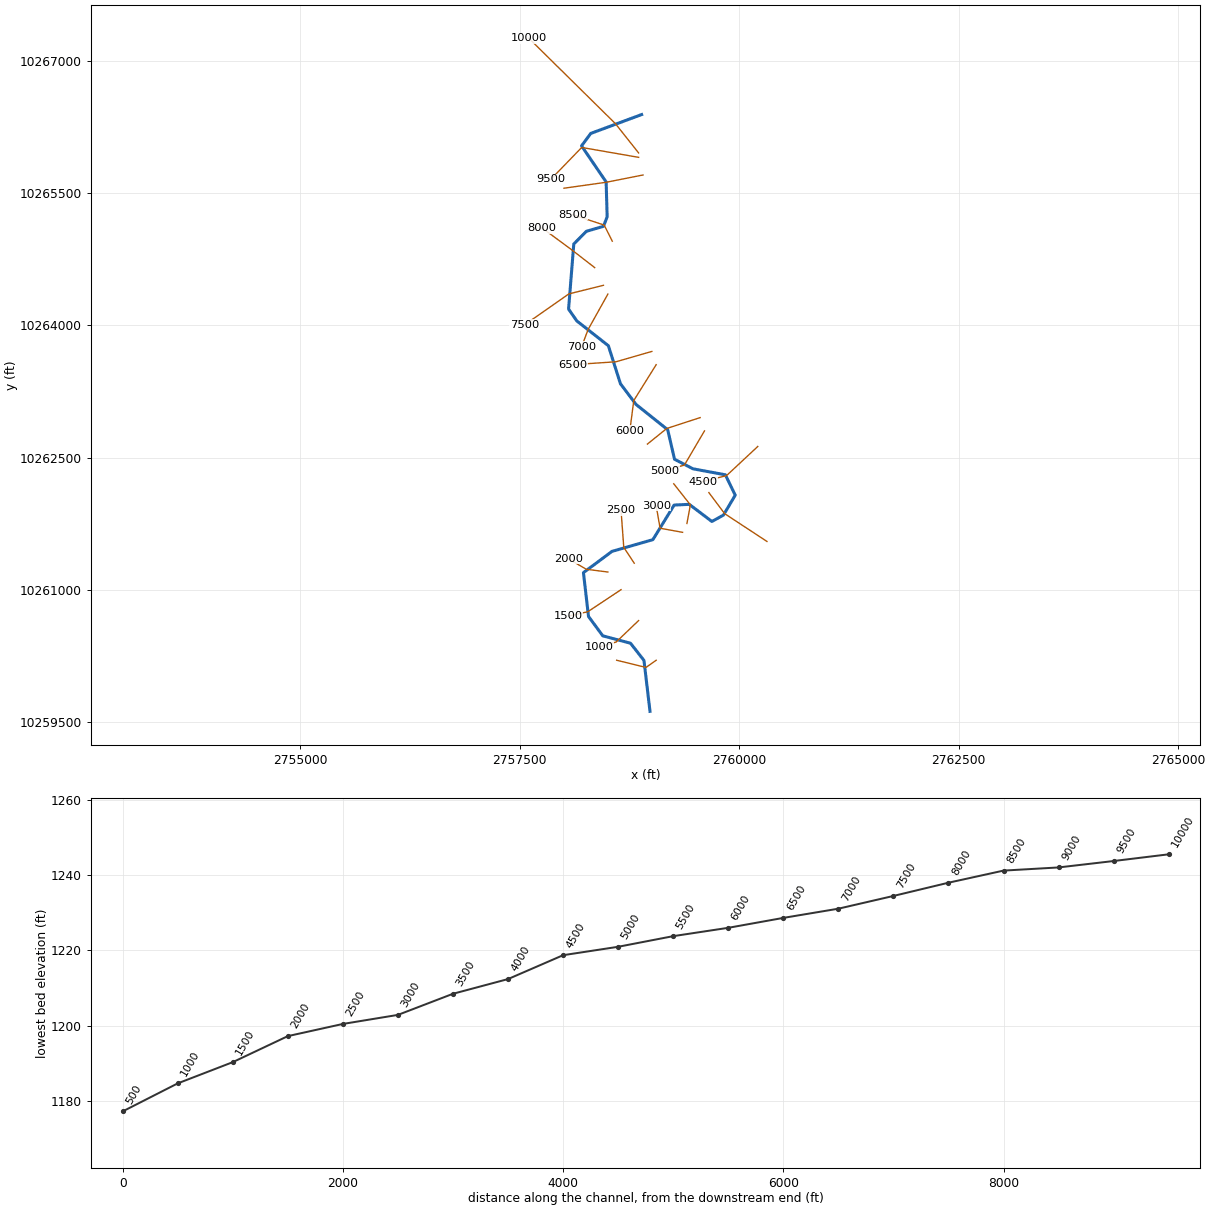
--- SANFERNANDO023.prj (project) ---

Proj Title=SANFERNANDO023 Base Level Engineering
Current Plan=p01
Default Exp/Contr=0.3,0.1
English Units
Geom File=g01
Flow File=f01
Plan File=p01
BEGIN DESCRIPTION:
SANFERNANDO023
END DESCRIPTION:

--- SANFERNANDO023.p01 (plan) ---

Plan Title=Multiple Run
Short Identifier=Multiple
Geom File=g01
Flow File=f01
Subcritical Flow
K Sum by GR= 0
Std Step Tol= 0.01
Critical Tol= 0.01
Num of Std Step Trials= 20
Max Error Tol= 0.3
Flow Tol Ratio= 0.001
Split Flow NTrial= 30
Split Flow Tol= 0.02
Split Flow Ratio= 0.02
Log Output Level= 0
Friction Slope Method= 1
Unsteady Friction Slope Method= 2
Unsteady Bridges Friction Slope Method= 1
Parabolic Critical Depth
Global Vel Dist=  1 , 1 , 1
Global Log Level= 0
CheckData=True
Encroach Param= -1, 0, 0, 0
BEGIN DESCRIPTION:
Multiple Run
END DESCRIPTION:

--- SANFERNANDO023.f01 (steady flow) ---

Flow Title=Multiple
Number of Profiles=7
Profile Names=10-year,25-year,50-year,1pct_min,100-year,1pct_plu,500-year
River Rch & RM= SANFERNANDO023,Reach-1,10000
    1089    1877    2329    1345    3161    7429    4265
River Rch & RM= SANFERNANDO023,Reach-1,5000
    1308    2281    2951    2363    4045    6925    5473
River Rch & RM= SANFERNANDO023,Reach-1,2000
    1382    2422    3233    2338    4462    8516    6070
Boundary for River Rch & Prof#=SANFERNANDO023,Reach-1,1
Up Type=0
Dn Type=3
Dn Slope=0.005
Boundary for River Rch & Prof#=SANFERNANDO023,Reach-1,2
Up Type=0
Dn Type=3
Dn Slope=0.005
Boundary for River Rch & Prof#=SANFERNANDO023,Reach-1,3
Up Type=0
Dn Type=3
Dn Slope=0.005
Boundary for River Rch & Prof#=SANFERNANDO023,Reach-1,4
Up Type=0
Dn Type=3
Dn Slope=0.005
Boundary for River Rch & Prof#=SANFERNANDO023,Reach-1,5
Up Type=0
Dn Type=3
Dn Slope=0.005
Boundary for River Rch & Prof#=SANFERNANDO023,Reach-1,6
Up Type=0
Dn Type=3
Dn Slope=0.005
Boundary for River Rch & Prof#=SANFERNANDO023,Reach-1,7
Up Type=0
Dn Type=3
Dn Slope=0.005

--- SANFERNANDO023.g01 (geometry) ---

Geom Title=Existing Conditions

River Reach=SANFERNANDO023,Reach-1
Reach XY= 30
      2758889.75     10266388.00      2758310.50     10266174.00
      2758206.25     10266033.00      2758486.00     10265624.00
      2758497.50     10265228.00      2758455.00     10265121.00
      2758261.25     10265065.00      2758117.50     10264921.00
      2758058.25     10264183.00      2758152.00     10264049.00
      2758511.25     10263768.00      2758648.75     10263337.00
      2758826.75     10263102.00      2759186.50     10262816.00
      2759264.75     10262481.00      2759474.50     10262373.00
      2759843.25     10262305.00      2759955.75     10262074.00
      2759821.25     10261848.00      2759690.00     10261776.00
      2759432.25     10261970.00      2759260.25     10261962.00
      2759018.25     10261570.00      2758552.50     10261437.00
      2758227.50     10261196.00      2758285.25     10260699.00
      2758447.75     10260480.00      2758763.50     10260396.00
      2758916.50     10260201.00      2758985.25     10259624.00

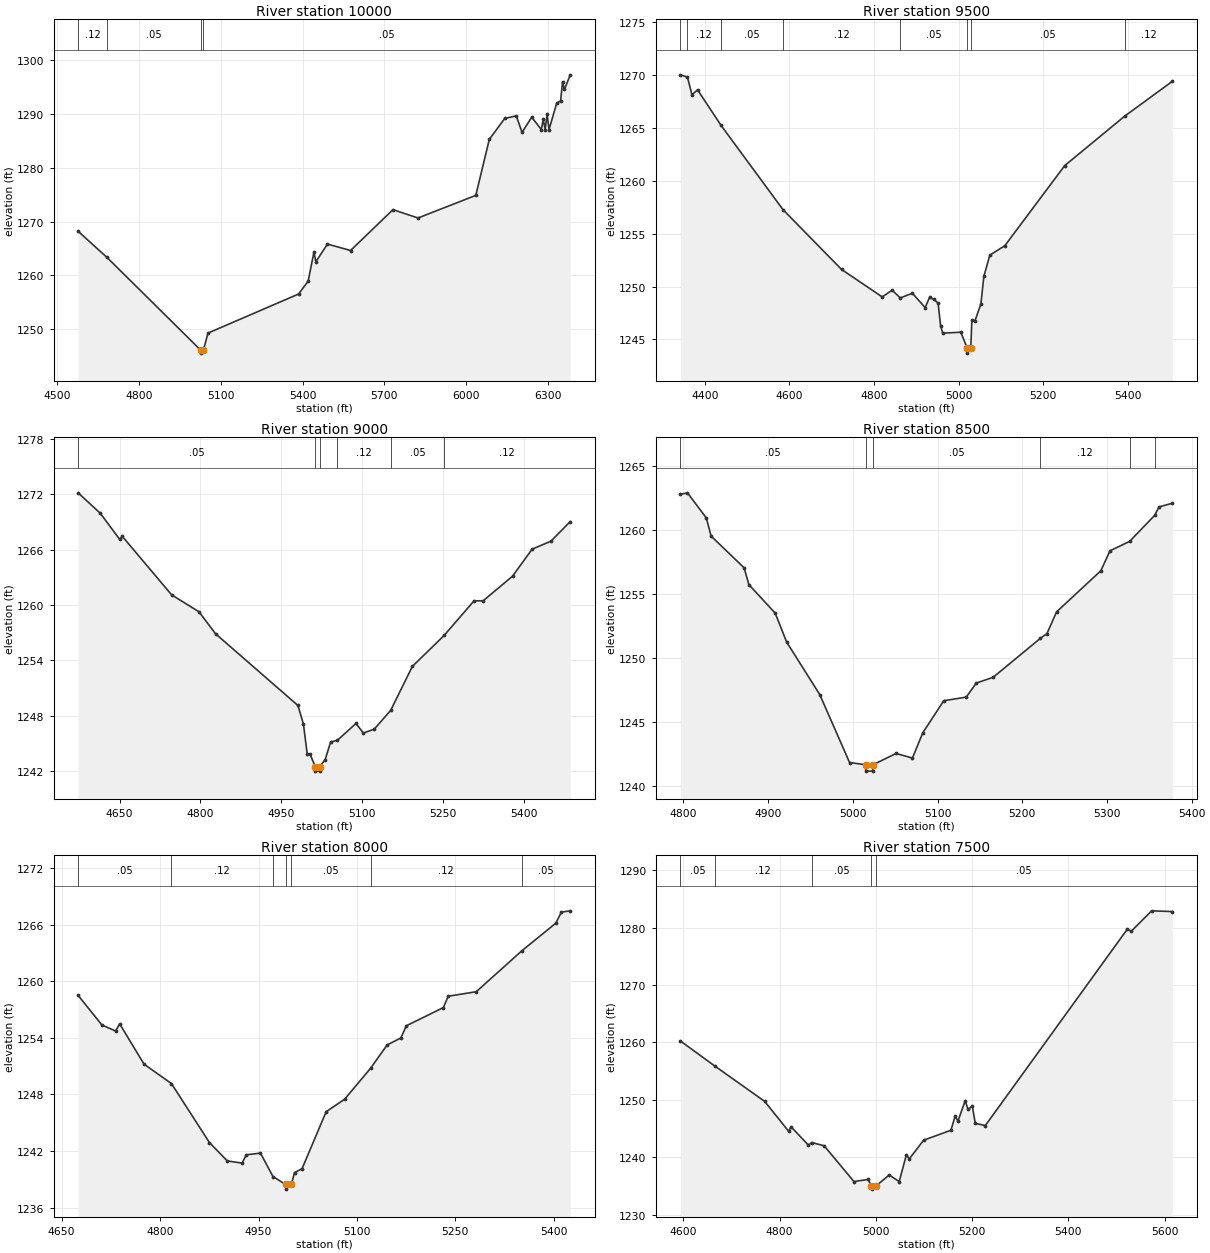
Type RM Length L Ch R = 1,10000,500,500,500
BEGIN DESCRIPTION:
SANFERNANDO023 20.0
END DESCRIPTION:
XS GIS Cut Line= 3
      2758855.66     10265953.15      2758591.85     10266284.57
      2757605.71     10267253.08
#Sta/Elev= 30
  4576.4 1268.18  4682.5 1263.30  5027.3 1245.98  5027.8 1245.48  5035.9 1245.98
  5052.8 1249.21  5385.2 1256.49  5420.5 1258.88  5441.8 1264.33  5448.8 1262.50
  5491.2 1265.80  5576.1 1264.60  5731.7 1272.21  5823.6 1270.66  6035.7 1274.87
  6085.3 1285.31  6141.9 1289.20  6184.3 1289.69  6205.4 1286.61  6240.9 1289.44
  6276.2 1287.12  6283.3 1289.03  6290.3 1287.14  6297.4 1289.94  6304.5 1287.14
  6332.7 1292.08  6346.9 1292.44  6354.0 1296.06  6361.0 1294.60  6382.2 1297.33
#Mann=4,-1,0
  4576.4    0.12       0  4682.5    0.05       0  5027.3    0.05       0
  5035.9    0.05       0
Bank Sta=5027.3,5035.9
Exp/Cntr=0.3,0.1

Type RM Length L Ch R = 1,9500,500,500,500
BEGIN DESCRIPTION:
SANFERNANDO023 19.0
END DESCRIPTION:
XS GIS Cut Line= 3
      2758855.72     10265903.11      2758207.65     10266015.27
      2757855.69     10265653.12
#Sta/Elev= 30
  4342.3 1270.04  4359.1 1269.82  4369.7 1268.15  4382.9 1268.62  4438.2 1265.27
  4584.8 1257.28  4723.2 1251.62  4819.3 1249.02  4842.7 1249.66  4862.0 1248.92
  4890.4 1249.37  4920.8 1248.01  4931.0 1248.97  4941.1 1248.78  4951.3 1248.44
  4957.2 1246.29  4962.3 1245.59  5005.0 1245.68  5019.8 1244.20  5020.3 1243.70
  5028.5 1244.20  5031.1 1246.82  5038.3 1246.75  5052.4 1248.35  5059.4 1250.96
  5073.5 1252.97  5109.0 1253.87  5250.5 1261.45  5391.9 1266.12  5505.0 1269.43
#Mann=8,-1,0
  4342.3    0.05       0  4359.1    0.12       0  4438.2    0.05       0
  4584.8    0.12       0  4862.0    0.05       0  5019.8    0.03       0
  5028.5    0.05       0  5391.9    0.12       0
Bank Sta=5019.8,5028.5
Exp/Cntr=0.3,0.1

Type RM Length L Ch R = 1,9000,500,500,500
BEGIN DESCRIPTION:
SANFERNANDO023 18.0
END DESCRIPTION:
XS GIS Cut Line= 3
      2758905.68     10265703.11      2758486.82     10265620.61
      2758005.64     10265553.10
#Sta/Elev= 30
  4573.1 1272.18  4613.9 1269.98  4650.1 1267.14  4655.2 1267.45  4746.4 1261.12
  4797.3 1259.28  4827.9 1256.90  4980.8 1249.12  4991.0 1247.11  4998.0 1243.88
  5003.1 1243.88  5012.8 1242.50  5013.3 1242.00  5021.0 1242.00  5021.5 1242.50
  5031.4 1243.26  5041.5 1245.17  5053.7 1245.33  5088.5 1247.17  5102.1 1246.13
  5122.3 1246.55  5152.8 1248.58  5193.0 1253.35  5251.9 1256.71  5307.5 1260.47
  5324.3 1260.47  5378.9 1263.14  5415.2 1266.07  5450.2 1266.94  5485.9 1269.06
#Mann=6,-1,0
  4573.1    0.05       0  5012.8    0.05       0  5021.5    0.05       0
  5053.7    0.12       0  5152.8    0.05       0  5251.9    0.12       0
Bank Sta=5012.8,5021.5
Exp/Cntr=0.3,0.1

Type RM Length L Ch R = 1,8500,500,500,500
BEGIN DESCRIPTION:
SANFERNANDO023 17.0
END DESCRIPTION:
XS GIS Cut Line= 3
      2758555.69     10264953.09      2758464.08     10265135.03
      2758105.73     10265253.10
#Sta/Elev= 30
  4796.3 1262.78  4804.7 1262.90  4827.0 1260.93  4832.6 1259.52  4871.6 1257.04
  4877.2 1255.73  4908.3 1253.50  4921.8 1251.24  4960.9 1247.14  4996.1 1241.83
  5015.0 1241.66  5015.5 1241.16  5023.3 1241.16  5023.8 1241.66  5051.0 1242.54
  5070.3 1242.18  5082.5 1244.15  5107.3 1246.66  5133.8 1246.94  5145.7 1248.04
  5165.6 1248.49  5221.3 1251.53  5229.1 1251.90  5240.5 1253.60  5292.7 1256.81
  5303.6 1258.37  5326.8 1259.11  5356.2 1261.13  5361.5 1261.80  5377.3 1262.09
#Mann=6,-1,0
  4796.3    0.05       0  5015.0    0.03       0  5023.8    0.05       0
  5221.3    0.12       0  5326.8    0.05       0  5356.2    0.12       0
Bank Sta=5015,5023.8
Exp/Cntr=0.3,0.1

Type RM Length L Ch R = 1,8000,500,500,500
BEGIN DESCRIPTION:
SANFERNANDO023 16.0
END DESCRIPTION:
XS GIS Cut Line= 3
      2758355.65     10264653.14      2758098.52     10264851.74
      2757755.70     10265103.10
#Sta/Elev= 30
  4675.1 1258.50  4711.3 1255.36  4732.1 1254.72  4738.4 1255.48  4775.6 1251.20
  4817.3 1249.15  4875.2 1242.89  4902.5 1240.94  4925.0 1240.71  4931.4 1241.59
  4953.0 1241.77  4972.1 1239.28  4991.2 1238.45  4991.7 1237.95  5000.1 1238.45
  5004.9 1239.70  5016.4 1240.12  5053.1 1246.16  5081.3 1247.49  5120.7 1250.76
  5146.1 1253.25  5166.9 1253.98  5175.4 1255.28  5231.8 1257.21  5239.1 1258.41
  5281.9 1258.89  5351.0 1263.21  5403.1 1266.16  5411.6 1267.33  5425.1 1267.47
#Mann=7,-1,0
  4675.1    0.05       0  4817.3    0.12       0  4972.1    0.05       0
  4991.2    0.05       0  5000.1    0.05       0  5120.7    0.12       0
  5351.0    0.05       0
Bank Sta=4991.2,5000.1
Exp/Cntr=0.3,0.1

Type RM Length L Ch R = 1,7500,500,500,500
BEGIN DESCRIPTION:
SANFERNANDO023 15.0
END DESCRIPTION:
XS GIS Cut Line= 3
      2758455.65     10264453.10      2758061.51     10264355.26
      2757555.71     10264003.13
#Sta/Elev= 30
  4593.9 1260.25  4665.5 1255.88  4769.0 1249.73  4818.8 1244.53  4823.9 1245.30
  4860.1 1242.09  4866.9 1242.56  4892.7 1241.99  4954.5 1235.76  4984.2 1236.13
  4990.8 1234.94  4991.3 1234.44  4999.7 1234.94  5027.7 1236.90  5048.6 1235.76
  5063.5 1240.42  5069.6 1239.71  5099.3 1242.96  5156.0 1244.69  5164.7 1247.13
  5170.8 1246.32  5185.7 1249.84  5191.7 1248.32  5200.5 1248.92  5206.6 1245.90
  5227.5 1245.51  5522.5 1279.71  5531.0 1279.37  5573.1 1282.91  5616.3 1282.78
#Mann=5,-1,0
  4593.9    0.05       0  4665.5    0.12       0  4866.9    0.05       0
  4990.8    0.03       0  4999.7    0.05       0
Bank Sta=4990.8,4999.7
Exp/Cntr=0.3,0.1

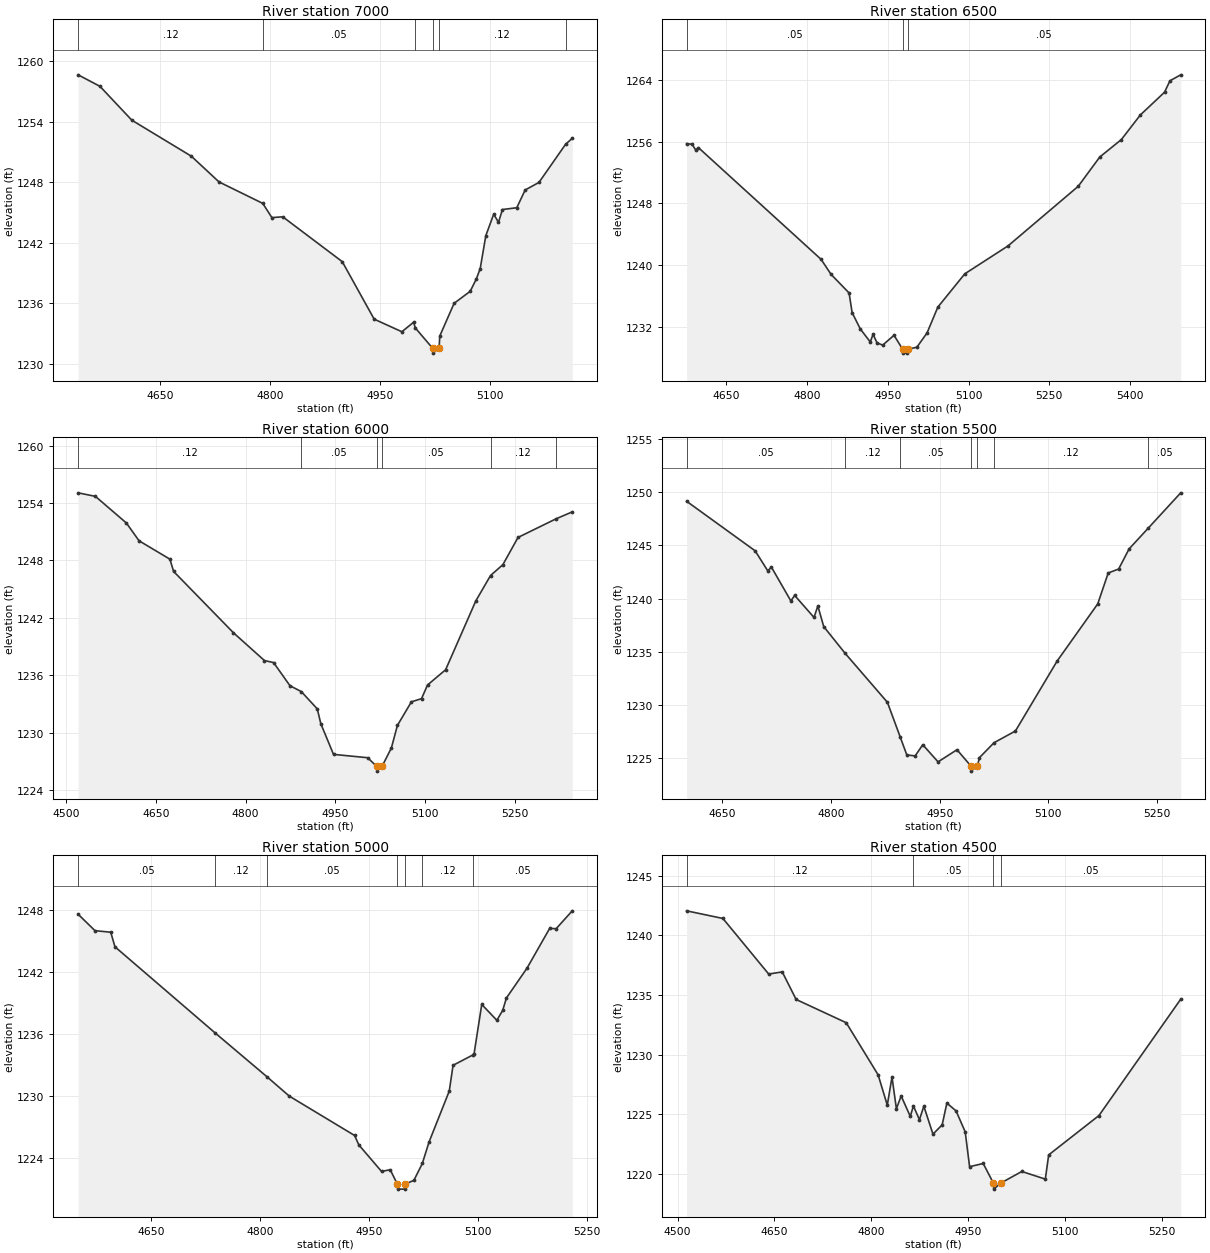
Type RM Length L Ch R = 1,7000,500,500,500
BEGIN DESCRIPTION:
SANFERNANDO023 14.0
END DESCRIPTION:
XS GIS Cut Line= 3
      2758505.70     10264353.13      2758280.24     10263950.91
      2758205.68     10263753.10
#Sta/Elev= 30
  4538.9 1258.66  4568.6 1257.52  4612.0 1254.16  4693.0 1250.59  4730.6 1248.04
  4790.2 1245.91  4802.6 1244.50  4817.4 1244.58  4898.4 1240.13  4941.8 1234.43
  4979.5 1233.18  4995.4 1234.12  4997.9 1233.55  5021.2 1231.56  5021.7 1231.06
  5030.2 1231.56  5031.1 1232.76  5050.6 1236.00  5072.5 1237.19  5080.8 1238.41
  5086.1 1239.44  5093.8 1242.72  5104.5 1244.84  5111.0 1244.03  5116.4 1245.30
  5135.9 1245.48  5147.3 1247.24  5166.1 1247.99  5202.2 1251.76  5211.4 1252.37
#Mann=6,-1,0
  4538.9    0.12       0  4790.2    0.05       0  4997.9    0.12       0
  5021.2    0.07       0  5030.2    0.12       0  5202.2    0.05       0
Bank Sta=5021.2,5030.2
Exp/Cntr=0.3,0.1

Type RM Length L Ch R = 1,6500,500,500,500
BEGIN DESCRIPTION:
SANFERNANDO023 13.0
END DESCRIPTION:
XS GIS Cut Line= 3
      2759005.72     10263703.12      2758598.50     10263586.11
      2758105.71     10263553.11
#Sta/Elev= 30
  4576.3 1255.74  4586.7 1255.66  4593.2 1254.92  4598.4 1255.22  4826.1 1240.76
  4844.8 1238.80  4878.1 1236.41  4883.7 1233.87  4898.9 1231.75  4917.4 1230.07
  4922.6 1231.05  4930.1 1229.94  4940.5 1229.66  4961.5 1230.93  4977.6 1229.12
  4978.1 1228.62  4986.2 1228.62  4986.7 1229.12  5003.9 1229.38  5022.9 1231.24
  5042.9 1234.58  5093.0 1238.89  5173.2 1242.50  5303.5 1250.21  5343.6 1254.01
  5383.7 1256.27  5418.9 1259.45  5463.9 1262.40  5473.9 1263.88  5493.9 1264.65
#Mann=3,-1,0
  4576.3    0.05       0  4977.6    0.05       0  4986.7    0.05       0
Bank Sta=4977.6,4986.7
Exp/Cntr=0.3,0.1

Type RM Length L Ch R = 1,6000,500,500,500
BEGIN DESCRIPTION:
SANFERNANDO023 12.0
END DESCRIPTION:
XS GIS Cut Line= 3
      2759055.70     10263553.14      2758800.45     10263146.63
      2758755.69     10262803.14
#Sta/Elev= 30
  4520.0 1255.06  4548.9 1254.69  4600.7 1251.91  4621.9 1250.05  4673.5 1248.13
  4679.7 1246.85  4779.8 1240.44  4831.6 1237.54  4846.9 1237.33  4874.3 1234.91
  4893.2 1234.30  4920.0 1232.49  4925.9 1230.94  4947.1 1227.74  5004.3 1227.39
  5019.2 1226.49  5019.7 1225.99  5028.3 1226.49  5043.9 1228.41  5054.0 1230.77
  5077.4 1233.23  5094.3 1233.56  5104.4 1234.99  5134.6 1236.58  5185.1 1243.77
  5209.7 1246.42  5230.4 1247.56  5255.7 1250.40  5319.1 1252.34  5346.4 1253.07
#Mann=6,-1,0
  4520.0    0.12       0  4893.2    0.05       0  5019.2    0.03       0
  5028.3    0.05       0  5209.7    0.12       0  5319.1    0.05       0
Bank Sta=5019.2,5028.3
Exp/Cntr=0.3,0.1

Type RM Length L Ch R = 1,5500,500,500,500
BEGIN DESCRIPTION:
SANFERNANDO023 11.0
END DESCRIPTION:
XS GIS Cut Line= 3
      2759555.64     10262953.10      2759176.00     10262830.00
      2758955.71     10262653.14
#Sta/Elev= 30
  4600.9 1249.14  4695.5 1244.48  4712.8 1242.61  4718.0 1242.94  4744.8 1239.77
  4750.0 1240.29  4776.7 1238.22  4782.0 1239.30  4790.1 1237.36  4819.6 1234.85
  4877.9 1230.25  4895.8 1226.95  4904.7 1225.30  4916.2 1225.21  4926.7 1226.26
  4947.8 1224.65  4973.9 1225.79  4992.9 1224.28  4993.4 1223.78  5002.1 1224.28
  5004.9 1225.05  5025.0 1226.45  5054.5 1227.55  5112.1 1234.13  5168.1 1239.50
  5182.5 1242.40  5196.9 1242.77  5211.3 1244.66  5237.3 1246.58  5282.5 1249.93
#Mann=7,-1,0
  4600.9    0.05       0  4819.6    0.12       0  4895.8    0.05       0
  4992.9    0.05       0  5002.1    0.05       0  5025.0    0.12       0
  5237.3    0.05       0
Bank Sta=4992.9,5002.1
Exp/Cntr=0.3,0.1

Type RM Length L Ch R = 1,5000,500,500,500
BEGIN DESCRIPTION:
SANFERNANDO023 10.0
END DESCRIPTION:
XS GIS Cut Line= 3
      2759605.68     10262803.11      2759376.67     10262414.81
      2759155.72     10262353.12
#Sta/Elev= 30
  4549.2 1247.56  4572.4 1245.97  4594.1 1245.82  4599.9 1244.41  4737.7 1236.08
  4809.2 1231.83  4839.9 1229.96  4929.8 1226.15  4935.6 1225.24  4966.9 1222.67
  4978.8 1222.84  4988.5 1221.46  4989.0 1220.96  4999.2 1220.96  4999.7 1221.46
  5011.4 1221.81  5023.0 1223.44  5032.2 1225.51  5060.1 1230.45  5065.3 1232.94
  5092.2 1233.93  5094.3 1234.08  5104.8 1238.83  5125.6 1237.30  5133.6 1238.25
  5138.8 1239.46  5167.1 1242.34  5198.3 1246.19  5207.2 1246.16  5229.4 1247.89
#Mann=7,-1,0
  4549.2    0.05       0  4737.7    0.12       0  4809.2    0.05       0
  4988.5    0.05       0  4999.7    0.05       0  5023.0    0.12       0
  5092.2    0.05       0
Bank Sta=4988.5,4999.7
Exp/Cntr=0.3,0.1

Type RM Length L Ch R = 1,4500,500,500,500
BEGIN DESCRIPTION:
SANFERNANDO023 9.0
END DESCRIPTION:
XS GIS Cut Line= 3
      2760212.27     10262626.12      2759856.25     10262295.29
      2759584.94     10262228.54
#Sta/Elev= 30
  4514.0 1242.06  4570.3 1241.42  4641.2 1236.76  4662.2 1236.94  4683.7 1234.63
  4761.3 1232.68  4810.7 1228.31  4824.9 1225.77  4832.2 1228.13  4839.0 1225.47
  4846.4 1226.54  4860.5 1224.83  4865.4 1225.70  4874.7 1224.55  4881.5 1225.68
  4895.7 1223.34  4909.9 1224.12  4917.2 1225.94  4931.4 1225.29  4945.6 1223.53
  4952.4 1220.61  4973.5 1220.88  4989.3 1219.23  4989.8 1218.73  5000.5 1219.23
  5033.3 1220.21  5069.7 1219.57  5074.9 1221.60  5152.8 1224.90  5279.4 1234.65
#Mann=4,-1,0
  4514.0    0.12       0  4865.4    0.05       0  4989.3    0.05       0
  5000.5    0.05       0
Bank Sta=4989.3,5000.5
Exp/Cntr=0.3,0.1

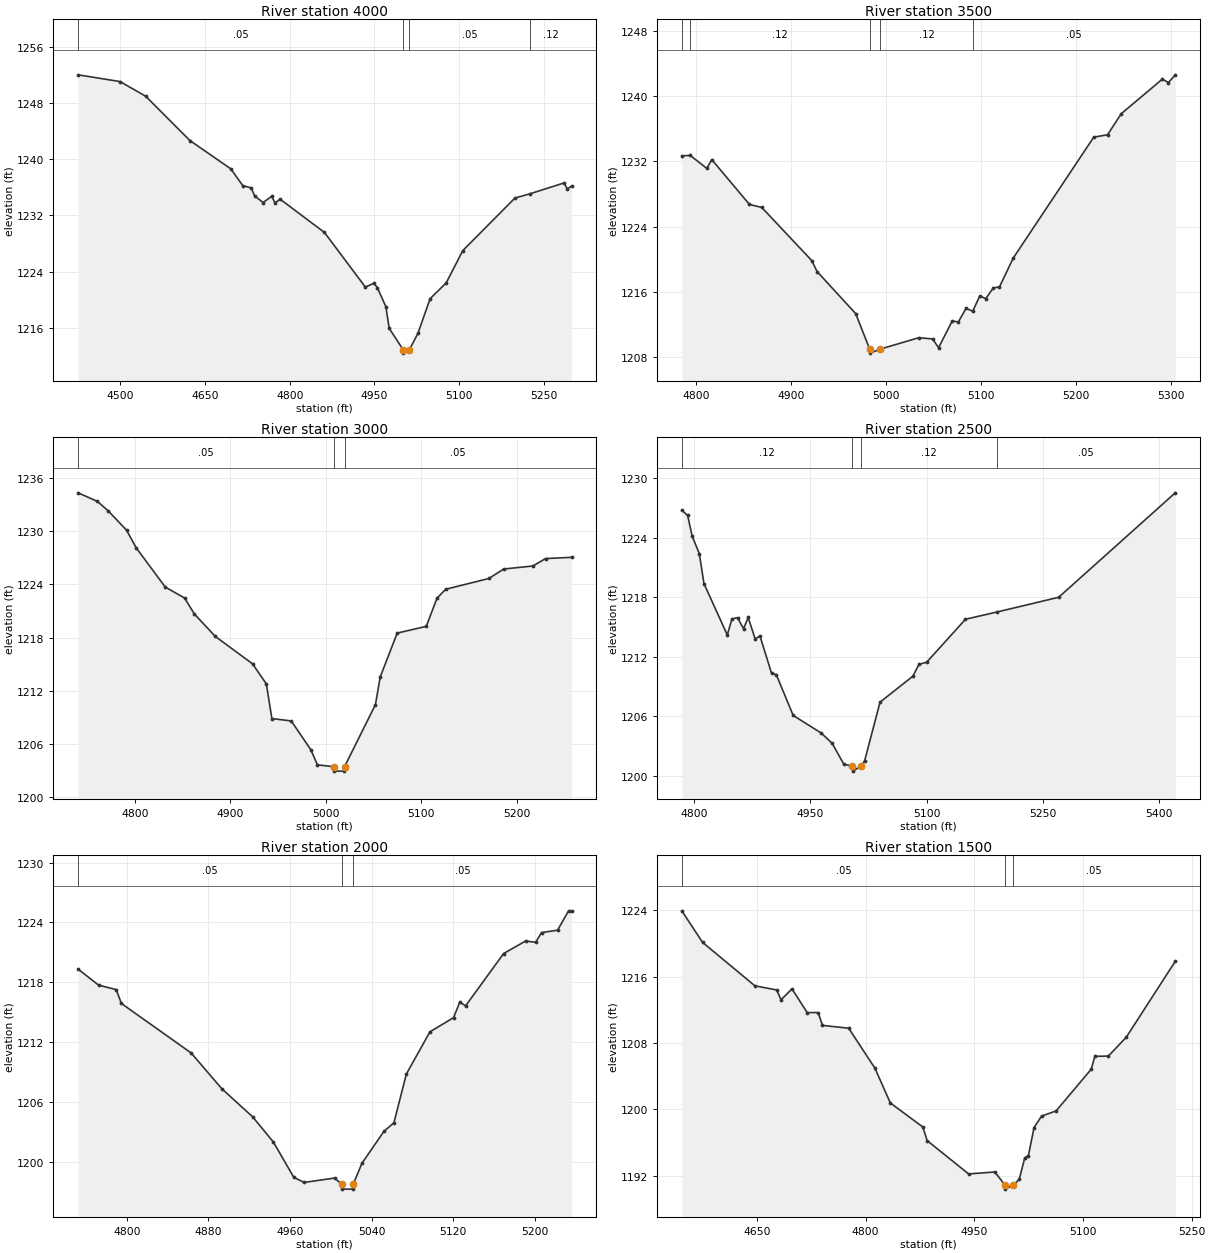
Type RM Length L Ch R = 1,4000,500,500,500
BEGIN DESCRIPTION:
SANFERNANDO023 8.0
END DESCRIPTION:
XS GIS Cut Line= 3
      2760316.40     10261549.76      2759835.46     10261864.37
      2759655.66     10262103.14
#Sta/Elev= 30
  4425.3 1252.02  4499.6 1251.06  4544.9 1248.98  4623.3 1242.66  4695.7 1238.64
  4716.7 1236.26  4731.8 1235.92  4737.8 1234.78  4752.9 1233.84  4768.0 1234.72
  4774.0 1233.79  4783.1 1234.31  4861.5 1229.58  4933.9 1221.80  4949.0 1222.35
  4955.0 1221.74  4970.1 1219.03  4976.1 1215.93  5000.7 1212.90  5001.2 1212.40
  5012.0 1212.90  5027.1 1215.24  5048.5 1220.15  5077.1 1222.41  5106.3 1226.99
  5198.7 1234.48  5225.2 1235.08  5285.3 1236.62  5291.6 1235.77  5298.9 1236.18
#Mann=4,-1,0
  4425.3    0.05       0  5000.7    0.05       0  5012.0    0.05       0
  5225.2    0.12       0
Bank Sta=5000.7,5012
Exp/Cntr=0.3,0.1

Type RM Length L Ch R = 1,3500,500,500,500
BEGIN DESCRIPTION:
SANFERNANDO023 7.0
END DESCRIPTION:
XS GIS Cut Line= 3
      2759405.68     10261753.08      2759445.04     10261964.14
      2759255.68     10262203.12
#Sta/Elev= 30
  4785.3 1232.67  4794.1 1232.73  4811.7 1231.13  4816.8 1232.22  4856.5 1226.72
  4869.5 1226.35  4922.2 1219.83  4927.7 1218.50  4968.4 1213.34  4983.1 1209.00
  4983.6 1208.50  4994.4 1209.00  5034.9 1210.39  5049.3 1210.24  5055.7 1209.17
  5070.1 1212.45  5076.5 1212.32  5084.6 1213.99  5091.6 1213.63  5099.0 1215.49
  5105.4 1215.19  5113.4 1216.50  5119.8 1216.61  5134.2 1220.13  5219.1 1234.97
  5233.6 1235.25  5248.0 1237.83  5291.3 1242.07  5297.7 1241.65  5304.9 1242.60
#Mann=5,-1,0
  4785.3    0.05       0  4794.1    0.12       0  4983.1    0.07       0
  4994.4    0.12       0  5091.6    0.05       0
Bank Sta=4983.1,4994.4
Exp/Cntr=0.3,0.1

Type RM Length L Ch R = 1,3000,500,500,500
BEGIN DESCRIPTION:
SANFERNANDO023 6.0
END DESCRIPTION:
XS GIS Cut Line= 3
      2759355.65     10261653.12      2759100.09     10261699.31
      2759055.68     10261953.15
#Sta/Elev= 30
  4740.3 1234.35  4760.6 1233.38  4772.1 1232.29  4791.1 1230.13  4801.2 1228.14
  4831.7 1223.70  4852.0 1222.46  4862.2 1220.66  4884.2 1218.12  4923.2 1215.03
  4937.7 1212.75  4943.5 1208.84  4963.8 1208.57  4984.2 1205.34  4991.3 1203.61
  5008.4 1203.40  5008.9 1202.90  5019.2 1202.90  5019.7 1203.40  5052.1 1210.42
  5057.1 1213.54  5074.9 1218.50  5105.4 1219.26  5116.6 1222.44  5125.7 1223.45
  5171.0 1224.67  5186.6 1225.74  5217.1 1226.08  5230.5 1226.92  5257.7 1227.06
#Mann=3,-1,0
  4740.3    0.05       0  5008.4    0.05       0  5019.7    0.05       0
Bank Sta=5008.4,5019.7
Exp/Cntr=0.3,0.1

Type RM Length L Ch R = 1,2500,500,500,500
BEGIN DESCRIPTION:
SANFERNANDO023 5.0
END DESCRIPTION:
XS GIS Cut Line= 3
      2758805.68     10261303.12      2758686.49     10261483.39
      2758655.68     10261903.16
#Sta/Elev= 30
  4783.9 1226.75  4791.4 1226.22  4797.4 1224.11  4806.5 1222.38  4812.5 1219.37
  4842.6 1214.20  4848.6 1215.81  4855.8 1215.94  4863.6 1214.83  4869.6 1215.96
  4878.7 1213.77  4884.7 1214.12  4899.8 1210.33  4905.8 1210.22  4927.7 1206.10
  4963.7 1204.34  4978.0 1203.30  4993.0 1201.20  5004.0 1201.00  5004.5 1200.50
  5015.4 1201.00  5019.8 1201.51  5039.8 1207.44  5082.2 1210.05  5090.0 1211.24
  5100.0 1211.46  5150.1 1215.78  5190.8 1216.51  5270.4 1217.99  5420.9 1228.50
#Mann=4,-1,0
  4783.9    0.12       0  5004.0    0.07       0  5015.4    0.12       0
  5190.8    0.05       0
Bank Sta=5004,5015.4
Exp/Cntr=0.3,0.1

Type RM Length L Ch R = 1,2000,500,500,500
BEGIN DESCRIPTION:
SANFERNANDO023 4.0
END DESCRIPTION:
XS GIS Cut Line= 3
      2758505.64     10261203.12      2758259.72     10261234.35
      2758055.67     10261353.12
#Sta/Elev= 30
  4752.1 1219.33  4772.2 1217.72  4789.5 1217.27  4794.6 1215.88  4862.9 1210.93
  4893.2 1207.32  4923.4 1204.51  4943.6 1202.00  4963.7 1198.45  4973.8 1197.94
  5003.7 1198.38  5010.5 1197.77  5011.0 1197.27  5021.5 1197.27  5022.0 1197.77
  5030.5 1199.86  5052.0 1203.05  5061.9 1203.93  5074.1 1208.81  5097.2 1213.04
  5120.4 1214.46  5126.5 1216.03  5132.2 1215.64  5169.5 1220.89  5191.0 1222.14
  5200.9 1222.02  5206.7 1222.99  5222.4 1223.23  5233.2 1225.17  5236.1 1225.17
#Mann=3,-1,0
  4752.1    0.05       0  5010.5    0.05       0  5022.0    0.05       0
Bank Sta=5010.5,5022
Exp/Cntr=0.3,0.1

Type RM Length L Ch R = 1,1500,500,500,500
BEGIN DESCRIPTION:
SANFERNANDO023 3.0
END DESCRIPTION:
XS GIS Cut Line= 3
      2758655.67     10261003.10      2758277.41     10260752.94
      2758055.65     10260703.10
#Sta/Elev= 30
  4546.5 1223.92  4575.1 1220.12  4647.3 1214.88  4677.4 1214.38  4683.4 1213.19
  4698.5 1214.51  4719.5 1211.65  4734.6 1211.66  4740.6 1210.11  4776.7 1209.77
  4812.8 1204.97  4834.2 1200.76  4879.0 1197.86  4885.0 1196.22  4942.2 1192.20
  4978.3 1192.44  4992.3 1190.87  4992.8 1190.37  5003.8 1190.87  5012.0 1191.54
  5019.6 1194.13  5024.7 1194.42  5032.5 1197.79  5042.8 1199.17  5062.9 1199.80
  5111.3 1204.82  5116.4 1206.38  5135.0 1206.41  5159.7 1208.68  5227.3 1217.83
#Mann=3,-1,0
  4546.5    0.05       0  4992.3    0.05       0  5003.8    0.05       0
Bank Sta=4992.3,5003.8
Exp/Cntr=0.3,0.1

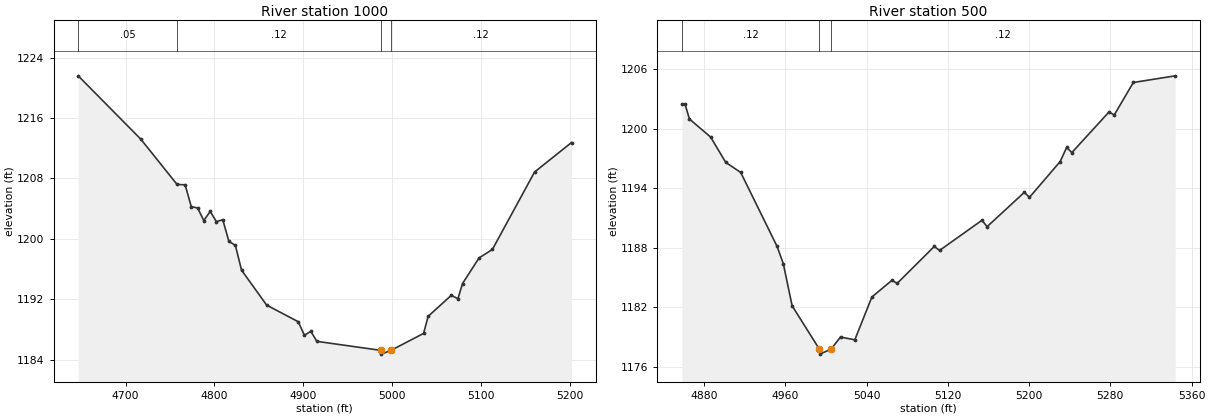
Type RM Length L Ch R = 1,1000,500,500,500
BEGIN DESCRIPTION:
SANFERNANDO023 2.0
END DESCRIPTION:
XS GIS Cut Line= 3
      2758855.72     10260653.14      2758599.80     10260409.42
      2758405.70     10260353.12
#Sta/Elev= 30
  4646.6 1221.59  4717.2 1213.19  4757.9 1207.21  4767.0 1207.16  4773.9 1204.28
  4781.1 1204.09  4788.0 1202.43  4795.3 1203.64  4802.2 1202.28  4809.4 1202.54
  4816.3 1199.67  4823.6 1199.14  4830.5 1195.87  4858.8 1191.23  4894.4 1189.03
  4901.3 1187.24  4908.5 1187.76  4915.4 1186.43  4987.3 1185.24  4987.8 1184.74
  4998.8 1185.24  5035.5 1187.48  5040.7 1189.75  5066.8 1192.53  5074.2 1192.07
  5079.4 1194.09  5098.0 1197.48  5113.0 1198.60  5160.5 1208.85  5202.1 1212.76
#Mann=4,-1,0
  4646.6    0.05       0  4757.9    0.12       0  4987.3    0.07       0
  4998.8    0.12       0
Bank Sta=4987.3,4998.8
Exp/Cntr=0.3,0.1

Type RM Length L Ch R = 1,500,0,0,0
BEGIN DESCRIPTION:
SANFERNANDO023 1.0
END DESCRIPTION:
XS GIS Cut Line= 3
      2759055.68     10260203.11      2758939.70     10260121.70
      2758605.68     10260203.11
#Sta/Elev= 30
  4858.3 1202.45  4861.4 1202.45  4865.7 1200.96  4886.6 1199.14  4901.4 1196.60
  4916.2 1195.58  4952.0 1188.14  4958.1 1186.41  4966.8 1182.17  4993.6 1177.81
  4994.1 1177.31  5005.1 1177.81  5014.4 1179.03  5028.5 1178.75  5045.3 1183.06
  5065.0 1184.73  5070.2 1184.43  5106.7 1188.14  5111.9 1187.74  5153.6 1190.77
  5158.7 1190.13  5195.3 1193.58  5200.4 1193.08  5230.6 1196.68  5237.0 1198.10
  5242.1 1197.58  5278.7 1201.67  5283.8 1201.36  5302.6 1204.63  5343.8 1205.30
#Mann=3,-1,0
  4858.3    0.12       0  4993.6    0.07       0  5005.1    0.12       0
Bank Sta=4993.6,5005.1
Exp/Cntr=0.3,0.1

Chan Stop Cuts=-1