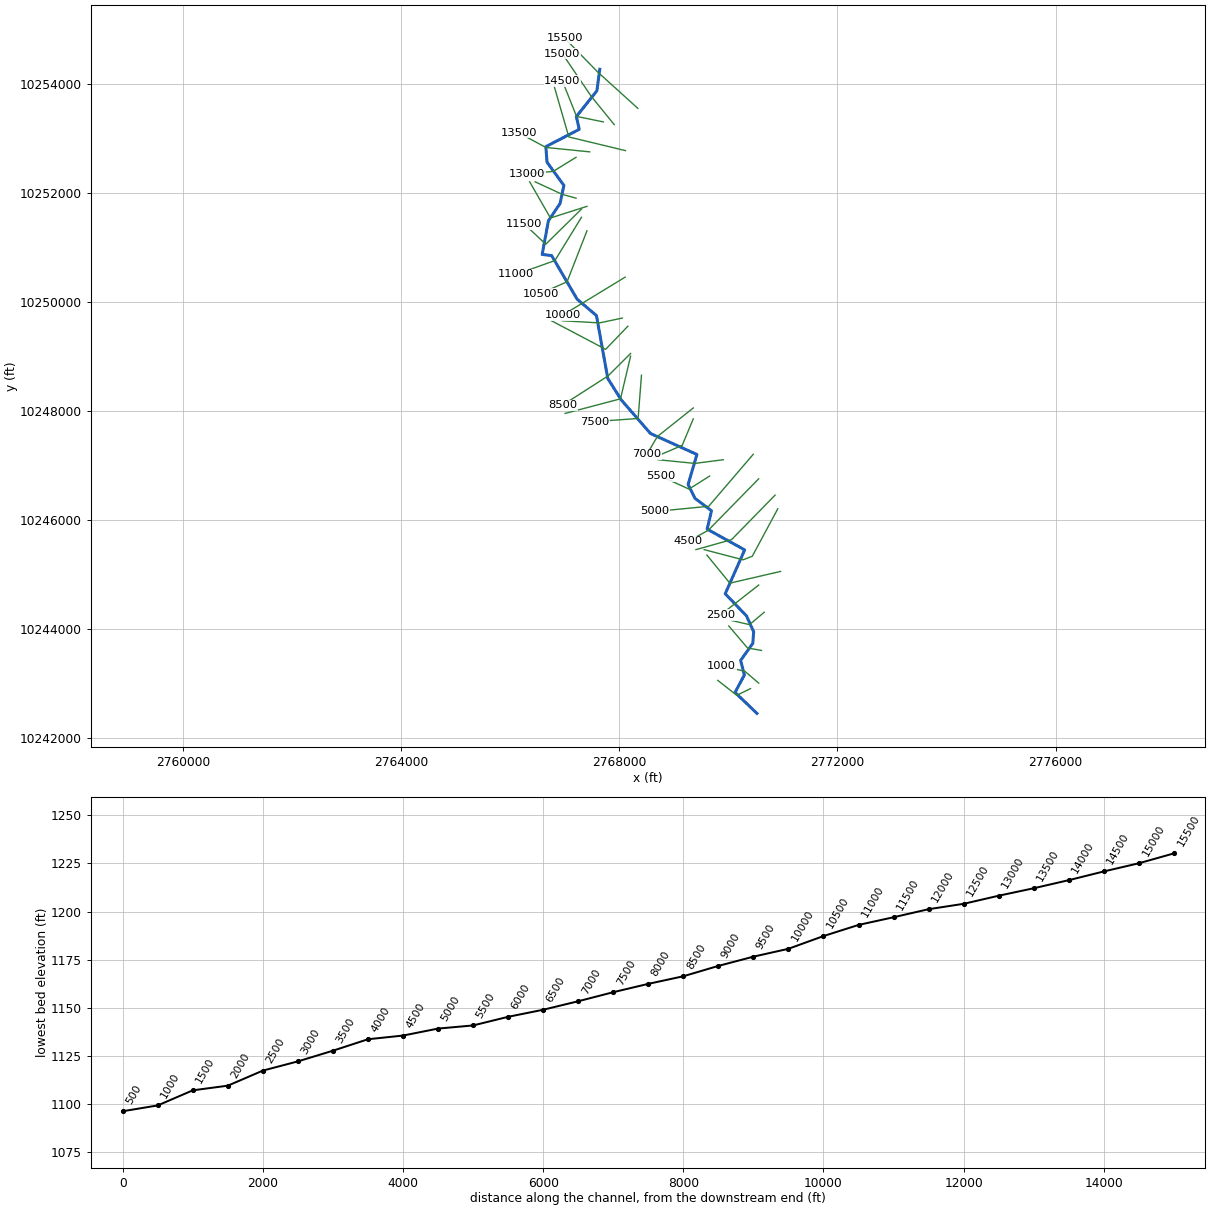
--- SANFERNANDO024.prj (project) ---

Proj Title=SANFERNANDO024 Base Level Engineering
Current Plan=p01
Default Exp/Contr=0.3,0.1
English Units
Geom File=g01
Flow File=f01
Plan File=p01
BEGIN DESCRIPTION:
SANFERNANDO024
END DESCRIPTION:

--- SANFERNANDO024.p01 (plan) ---

Plan Title=Multiple Run
Short Identifier=Multiple
Geom File=g01
Flow File=f01
Subcritical Flow
K Sum by GR= 0
Std Step Tol= 0.01
Critical Tol= 0.01
Num of Std Step Trials= 20
Max Error Tol= 0.3
Flow Tol Ratio= 0.001
Split Flow NTrial= 30
Split Flow Tol= 0.02
Split Flow Ratio= 0.02
Log Output Level= 0
Friction Slope Method= 1
Unsteady Friction Slope Method= 2
Unsteady Bridges Friction Slope Method= 1
Parabolic Critical Depth
Global Vel Dist=  1 , 1 , 1
Global Log Level= 0
CheckData=True
Encroach Param= -1, 0, 0, 0
BEGIN DESCRIPTION:
Multiple Run
END DESCRIPTION:

--- SANFERNANDO024.f01 (steady flow) ---

Flow Title=Multiple
Number of Profiles=7
Profile Names=10-year,25-year,50-year,1pct_min,100-year,1pct_plu,500-year
River Rch & RM= SANFERNANDO024,Reach-1,15500
     452     734     859     523    1129    2438    1526
River Rch & RM= SANFERNANDO024,Reach-1,6500
     726    1216    1555     984    2090    4440    2837
River Rch & RM= SANFERNANDO024,Reach-1,2000
     801    1353    1749    1023    2365    5468    3221
Boundary for River Rch & Prof#=SANFERNANDO024,Reach-1,1
Up Type=0
Dn Type=3
Dn Slope=0.005
Boundary for River Rch & Prof#=SANFERNANDO024,Reach-1,2
Up Type=0
Dn Type=3
Dn Slope=0.005
Boundary for River Rch & Prof#=SANFERNANDO024,Reach-1,3
Up Type=0
Dn Type=3
Dn Slope=0.005
Boundary for River Rch & Prof#=SANFERNANDO024,Reach-1,4
Up Type=0
Dn Type=3
Dn Slope=0.005
Boundary for River Rch & Prof#=SANFERNANDO024,Reach-1,5
Up Type=0
Dn Type=3
Dn Slope=0.005
Boundary for River Rch & Prof#=SANFERNANDO024,Reach-1,6
Up Type=0
Dn Type=3
Dn Slope=0.005
Boundary for River Rch & Prof#=SANFERNANDO024,Reach-1,7
Up Type=0
Dn Type=3
Dn Slope=0.005

--- SANFERNANDO024.g01 (geometry) ---

Geom Title=Existing Conditions

River Reach=SANFERNANDO024,Reach-1
Reach XY= 30
      2767641.00     10254269.00      2767587.75     10253874.00
      2767211.75     10253401.00      2767264.25     10253166.00
      2766651.75     10252849.00      2766674.00     10252562.00
      2766983.00     10252137.00      2766913.25     10251807.00
      2766699.00     10251487.00      2766584.50     10250871.00
      2766758.25     10250849.00      2767224.75     10250050.00
      2767580.25     10249748.00      2767788.00     10248594.00
      2768033.25     10248203.00      2768569.75     10247585.00
      2769422.75     10247199.00      2769260.25     10246649.00
      2769385.25     10246396.00      2769690.25     10246166.00
      2769609.50     10245830.00      2770298.25     10245448.00
      2769941.50     10244643.00      2770330.75     10244238.00
      2770463.00     10243947.00      2770447.25     10243734.00
      2770224.25     10243420.00      2770292.00     10243151.00
      2770121.75     10242833.00      2770522.50     10242448.00

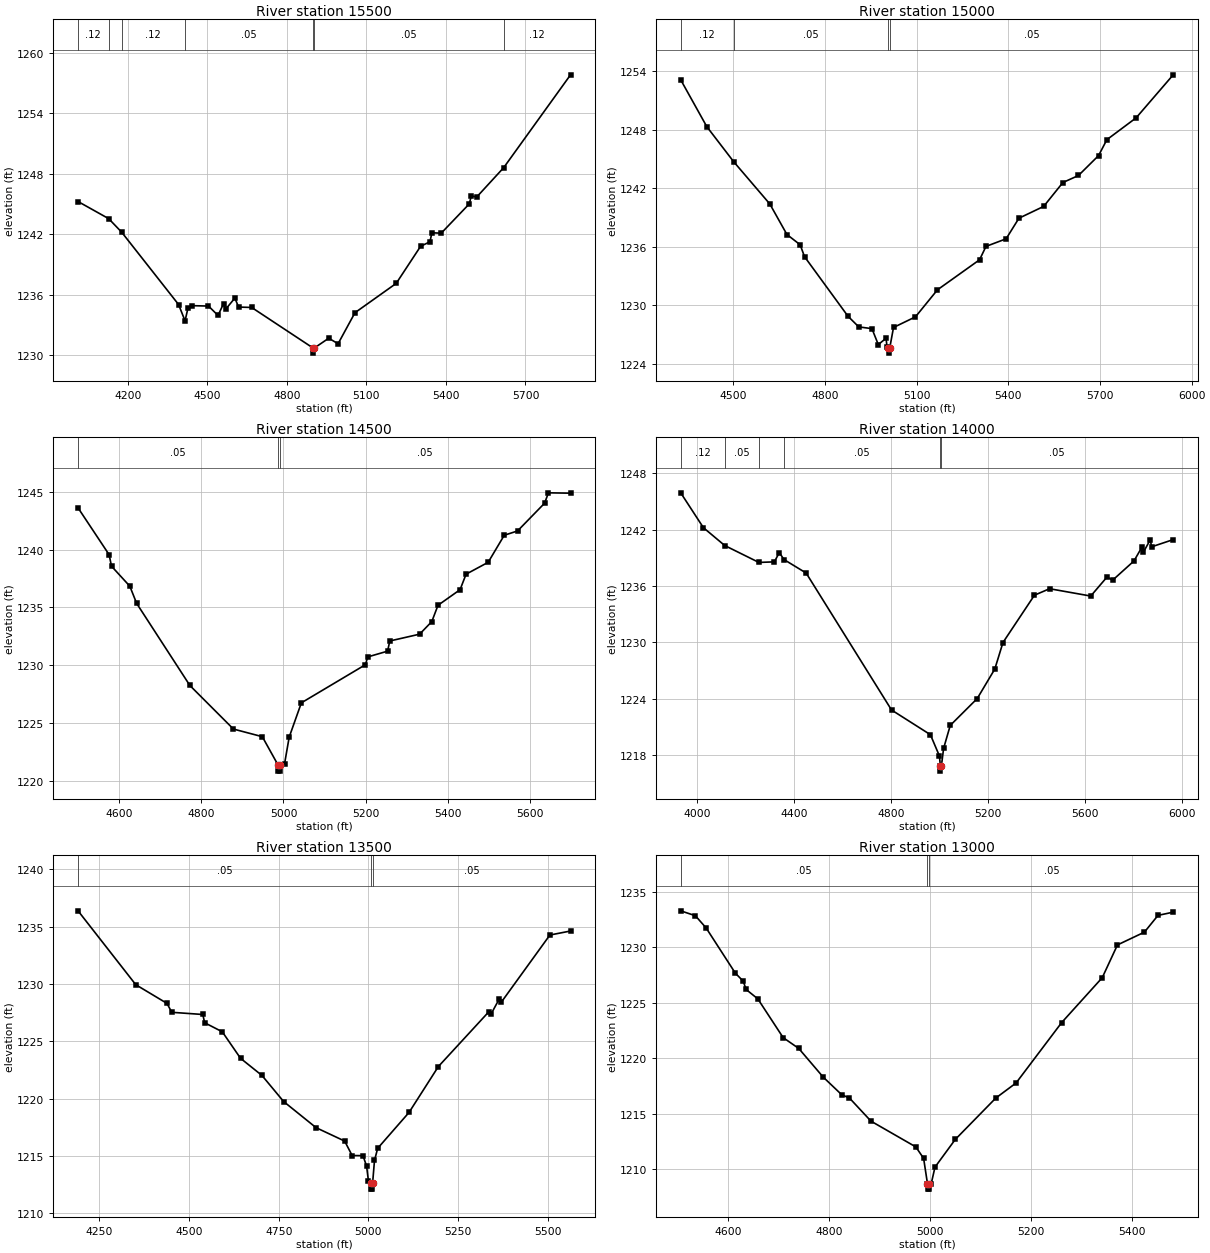
Type RM Length L Ch R = 1,15500,500,500,500
BEGIN DESCRIPTION:
SANFERNANDO024 31.0
END DESCRIPTION:
XS GIS Cut Line= 3
      2768339.35     10253551.41      2767607.46     10254214.36
      2766999.48     10254836.51
#Sta/Elev= 30
  4012.5 1245.24  4128.1 1243.54  4177.0 1242.20  4391.7 1235.02  4416.1 1233.40
  4426.8 1234.64  4441.0 1234.91  4504.5 1234.87  4540.4 1233.94  4561.3 1235.11
  4568.8 1234.54  4603.9 1235.66  4618.1 1234.77  4667.4 1234.73  4899.3 1230.70
  4899.5 1230.20  4903.3 1230.70  4958.0 1231.68  4993.2 1231.13  5056.9 1234.21
  5212.5 1237.12  5304.5 1240.80  5339.8 1241.25  5347.0 1242.14  5382.2 1242.10
  5488.2 1245.01  5495.4 1245.79  5516.5 1245.70  5617.8 1248.60  5869.9 1257.81
#Mann=7,-1,0
  4012.5    0.12       0  4128.1    0.05       0  4177.0    0.12       0
  4416.1    0.05       0  4899.3    0.03       0  4903.3    0.05       0
  5617.8    0.12       0
Bank Sta=4899.3,4903.3
Exp/Cntr=0.3,0.1

Type RM Length L Ch R = 1,15000,500,500,500
BEGIN DESCRIPTION:
SANFERNANDO024 30.0
END DESCRIPTION:
XS GIS Cut Line= 3
      2767905.65     10253253.15      2767482.32     10253774.91
      2766955.71     10254553.07
#Sta/Elev= 30
  4328.1 1253.10  4413.6 1248.29  4501.0 1244.72  4619.7 1240.37  4675.7 1237.24
  4718.9 1236.19  4733.2 1234.97  4875.5 1228.86  4910.7 1227.77  4953.8 1227.59
  4974.6 1225.96  5000.0 1226.60  5003.4 1225.67  5007.9 1225.58  5008.1 1225.08
  5011.9 1225.58  5024.4 1227.71  5096.3 1228.80  5168.2 1231.57  5306.0 1234.65
  5327.0 1236.02  5392.9 1236.80  5434.8 1238.91  5515.7 1240.12  5578.7 1242.57
  5629.6 1243.29  5695.4 1245.33  5722.5 1246.96  5818.3 1249.20  5939.6 1253.61
#Mann=4,-1,0
  4328.1    0.12       0  4501.0    0.05       0  5007.9    0.03       0
  5011.9    0.05       0
Bank Sta=5007.9,5011.9
Exp/Cntr=0.3,0.1

Type RM Length L Ch R = 1,14500,500,500,500
BEGIN DESCRIPTION:
SANFERNANDO024 29.0
END DESCRIPTION:
XS GIS Cut Line= 3
      2767705.65     10253303.12      2767215.18     10253403.32
      2766955.68     10254053.12
#Sta/Elev= 30
  4499.4 1243.61  4575.1 1239.56  4581.0 1238.56  4625.6 1236.83  4642.3 1235.34
  4772.0 1228.24  4878.1 1224.47  4948.5 1223.81  4987.3 1221.33  4987.5 1220.83
  4991.0 1220.83  4991.3 1221.33  5002.6 1221.44  5014.0 1223.77  5043.7 1226.74
  5199.9 1230.04  5205.3 1230.71  5253.8 1231.21  5259.2 1232.09  5331.9 1232.68
  5361.6 1233.77  5376.7 1235.18  5430.5 1236.53  5445.1 1237.87  5499.0 1238.90
  5538.2 1241.24  5570.5 1241.61  5636.4 1244.01  5645.9 1244.91  5699.7 1244.88
#Mann=3,-1,0
  4499.4    0.05       0  4987.3    0.05       0  4991.3    0.05       0
Bank Sta=4987.3,4991.3
Exp/Cntr=0.3,0.1

Type RM Length L Ch R = 1,14000,500,500,500
BEGIN DESCRIPTION:
SANFERNANDO024 28.0
END DESCRIPTION:
XS GIS Cut Line= 3
      2768111.20     10252776.01      2767073.45     10253026.70
      2766805.69     10253953.08
#Sta/Elev= 30
  3932.4 1245.93  4026.0 1242.22  4114.0 1240.32  4254.9 1238.52  4318.7 1238.58
  4339.3 1239.57  4358.3 1238.83  4449.9 1237.39  4802.2 1222.81  4962.6 1220.18
  5000.0 1217.90  5003.7 1216.80  5004.0 1216.30  5007.7 1216.80  5017.1 1218.73
  5044.5 1221.17  5155.8 1224.03  5228.3 1227.17  5261.9 1229.99  5391.8 1235.03
  5454.3 1235.72  5624.1 1234.94  5691.4 1236.97  5714.5 1236.63  5802.6 1238.68
  5836.2 1240.19  5841.5 1239.62  5869.9 1240.94  5875.1 1240.18  5964.3 1240.95
#Mann=6,-1,0
  3932.4    0.12       0  4114.0    0.05       0  4254.9    0.12       0
  4358.3    0.05       0  5003.7    0.03       0  5007.7    0.05       0
Bank Sta=5003.7,5007.7
Exp/Cntr=0.3,0.1

Type RM Length L Ch R = 1,13500,500,500,500
BEGIN DESCRIPTION:
SANFERNANDO024 27.0
END DESCRIPTION:
XS GIS Cut Line= 3
      2767455.68     10252753.11      2766650.56     10252834.33
      2766155.65     10253103.13
#Sta/Elev= 30
  4190.8 1236.37  4351.6 1229.93  4438.5 1228.30  4452.1 1227.52  4538.5 1227.33
  4543.6 1226.61  4592.8 1225.82  4643.6 1223.51  4703.4 1222.01  4763.7 1219.74
  4854.1 1217.46  4933.8 1216.29  4954.6 1215.03  4984.8 1215.02  4994.9 1214.11
  4999.9 1212.84  5007.6 1212.60  5007.8 1212.10  5011.3 1212.10  5011.6 1212.60
  5016.9 1214.60  5025.8 1215.66  5113.2 1218.79  5194.9 1222.79  5335.6 1227.57
  5342.2 1227.39  5364.1 1228.66  5369.8 1228.38  5505.7 1234.26  5563.2 1234.61
#Mann=3,-1,0
  4190.8    0.05       0  5007.6    0.03       0  5011.6    0.05       0
Bank Sta=5007.6,5011.6
Exp/Cntr=0.3,0.1

Type RM Length L Ch R = 1,13000,500,500,500
BEGIN DESCRIPTION:
SANFERNANDO024 26.0
END DESCRIPTION:
XS GIS Cut Line= 3
      2767205.72     10252653.14      2766785.32     10252394.11
      2766305.67     10252353.11
#Sta/Elev= 30
  4506.2 1233.28  4535.2 1232.84  4556.5 1231.74  4614.5 1227.66  4629.9 1226.95
  4635.7 1226.20  4658.9 1225.35  4709.1 1221.86  4739.9 1220.89  4788.3 1218.31
  4825.0 1216.72  4840.4 1216.42  4883.0 1214.34  4971.8 1212.02  4987.2 1210.99
  4994.8 1208.72  4995.1 1208.22  4998.6 1208.22  4998.8 1208.72  5002.3 1208.72
  5009.7 1210.20  5049.8 1212.69  5130.1 1216.42  5170.3 1217.78  5260.6 1223.22
  5340.9 1227.26  5371.0 1230.21  5424.4 1231.36  5451.3 1232.87  5481.4 1233.16
#Mann=3,-1,0
  4506.2    0.05       0  4994.8    0.03       0  4998.8    0.05       0
Bank Sta=4994.8,4998.8
Exp/Cntr=0.3,0.1

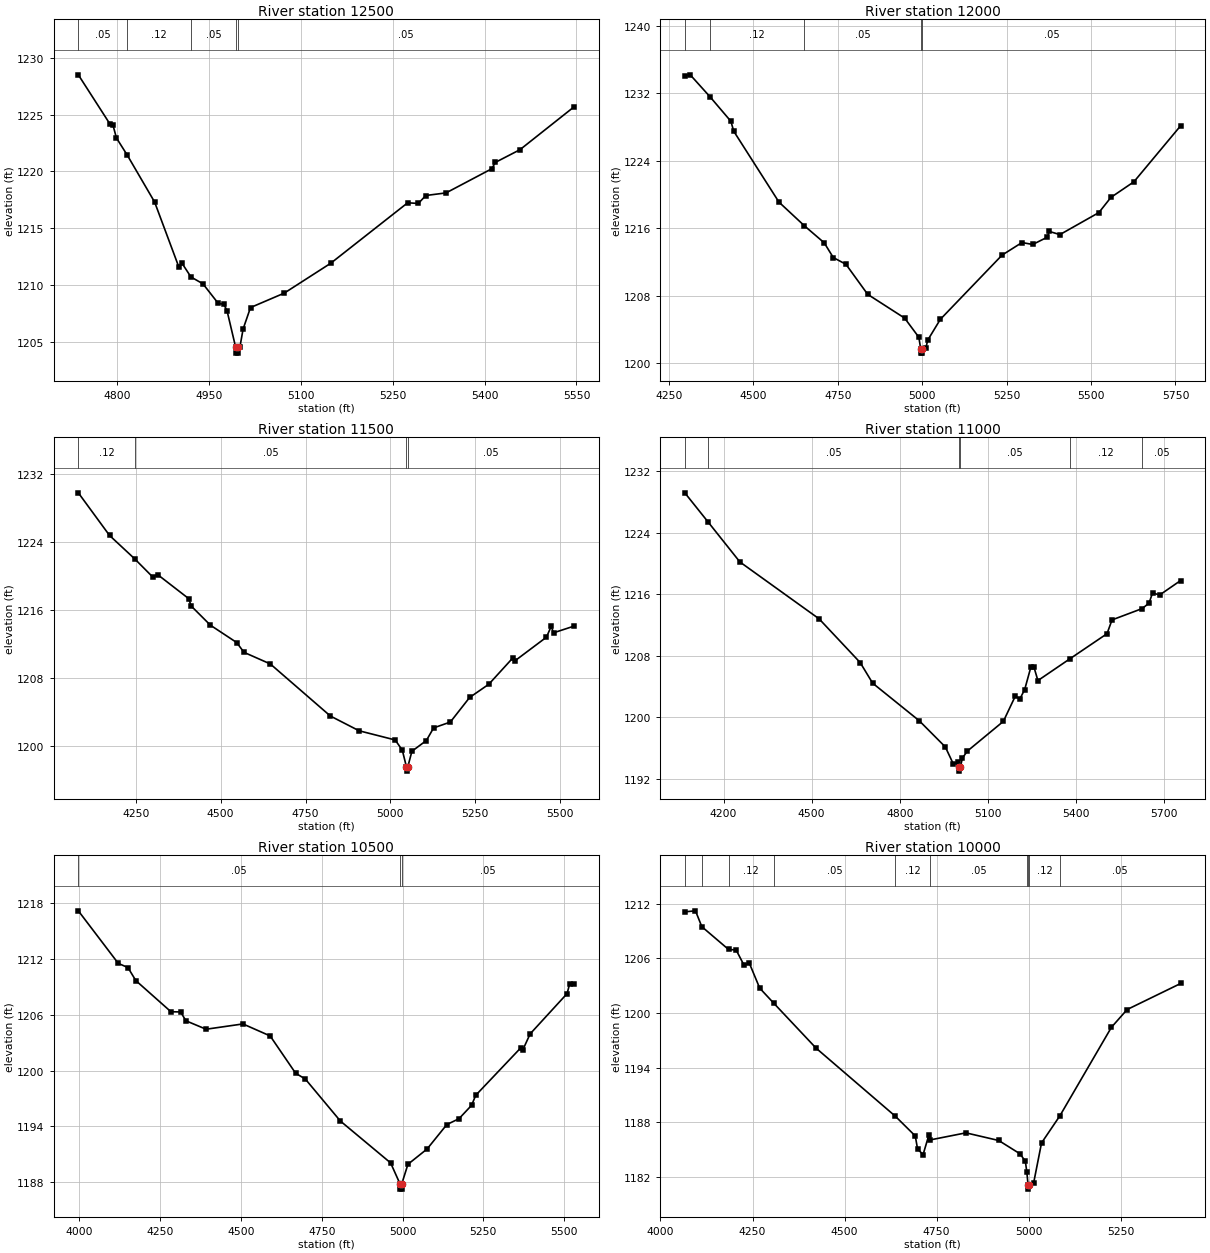
Type RM Length L Ch R = 1,12500,500,500,500
BEGIN DESCRIPTION:
SANFERNANDO024 25.0
END DESCRIPTION:
XS GIS Cut Line= 3
      2767205.70     10251903.11      2766951.50     10251974.02
      2766455.67     10252203.12
#Sta/Elev= 30
  4736.1 1228.50  4787.4 1224.20  4792.6 1224.09  4798.4 1222.94  4816.3 1221.41
  4860.7 1217.31  4900.3 1211.59  4905.5 1211.92  4920.1 1210.71  4939.7 1210.11
  4964.5 1208.40  4973.9 1208.30  4979.1 1207.73  4993.2 1204.51  4993.5 1204.01
  4997.0 1204.01  4997.2 1204.51  5000.0 1204.51  5005.3 1206.13  5017.4 1208.02
  5072.5 1209.29  5148.5 1211.92  5274.2 1217.24  5291.6 1217.18  5303.8 1217.88
  5336.9 1218.11  5411.8 1220.24  5417.3 1220.79  5457.6 1221.91  5546.2 1225.69
#Mann=5,-1,0
  4736.1    0.05       0  4816.3    0.12       0  4920.1    0.05       0
  4993.2    0.03       0  4997.2    0.05       0
Bank Sta=4993.2,4997.2
Exp/Cntr=0.3,0.1

Type RM Length L Ch R = 1,12000,500,500,500
BEGIN DESCRIPTION:
SANFERNANDO024 24.0
END DESCRIPTION:
XS GIS Cut Line= 3
      2767405.70     10251753.12      2766736.34     10251539.26
      2766355.70     10252203.08
#Sta/Elev= 30
  4297.3 1234.10  4313.4 1234.21  4372.1 1231.60  4433.8 1228.70  4442.1 1227.53
  4576.1 1219.12  4651.5 1216.31  4710.0 1214.30  4736.9 1212.55  4774.4 1211.75
  4838.7 1208.19  4948.2 1205.37  4990.2 1203.10  4995.7 1201.72  4996.0 1201.22
  4999.5 1201.22  4999.7 1201.72  5010.8 1201.80  5016.5 1202.76  5053.9 1205.23
  5236.6 1212.84  5295.6 1214.33  5327.2 1214.10  5370.4 1214.96  5376.1 1215.65
  5407.8 1215.27  5523.2 1217.88  5558.8 1219.68  5626.9 1221.53  5765.2 1228.17
#Mann=5,-1,0
  4297.3    0.05       0  4372.1    0.12       0  4651.5    0.05       0
  4995.7    0.03       0  4999.7    0.05       0
Bank Sta=4995.7,4999.7
Exp/Cntr=0.3,0.1

Type RM Length L Ch R = 1,11500,500,500,500
BEGIN DESCRIPTION:
SANFERNANDO024 23.0
END DESCRIPTION:
XS GIS Cut Line= 3
      2767305.70     10251703.13      2766650.61     10251058.03
      2766256.20     10251429.21
#Sta/Elev= 30
  4080.6 1229.81  4172.6 1224.79  4246.3 1222.05  4299.8 1219.90  4314.0 1220.19
  4405.9 1217.35  4413.0 1216.49  4469.6 1214.23  4547.3 1212.18  4568.6 1211.03
  4646.3 1209.66  4823.2 1203.53  4908.0 1201.79  5014.2 1200.71  5035.2 1199.51
  5047.4 1197.54  5047.6 1197.04  5051.4 1197.54  5063.5 1199.38  5106.0 1200.64
  5127.5 1202.13  5176.8 1202.82  5233.5 1205.71  5290.1 1207.27  5360.9 1210.37
  5367.8 1210.05  5459.9 1212.81  5473.8 1214.07  5481.1 1213.33  5541.6 1214.12
#Mann=4,-1,0
  4080.6    0.12       0  4246.3    0.05       0  5047.4    0.03       0
  5051.4    0.05       0
Bank Sta=5047.4,5051.4
Exp/Cntr=0.3,0.1

Type RM Length L Ch R = 1,11000,500,500,500
BEGIN DESCRIPTION:
SANFERNANDO024 22.0
END DESCRIPTION:
XS GIS Cut Line= 3
      2767305.67     10251553.08      2766818.24     10250758.59
      2766105.66     10250503.10
#Sta/Elev= 30
  4067.9 1229.15  4148.2 1225.32  4255.6 1220.18  4525.4 1212.80  4665.3 1207.13
  4707.9 1204.45  4866.5 1199.58  4955.4 1196.18  4983.0 1193.94  5000.0 1194.24
  5002.7 1193.54  5003.0 1193.04  5006.7 1193.54  5013.3 1194.71  5030.2 1195.63
  5153.2 1199.50  5193.9 1202.78  5209.3 1202.40  5225.8 1203.63  5247.1 1206.58
  5257.7 1206.49  5270.8 1204.79  5380.4 1207.63  5506.2 1210.87  5523.3 1212.66
  5625.8 1214.13  5649.3 1214.83  5661.4 1216.17  5685.4 1215.89  5757.0 1217.77
#Mann=6,-1,0
  4067.9    0.12       0  4148.2    0.05       0  5002.7    0.03       0
  5006.7    0.05       0  5380.4    0.12       0  5625.8    0.05       0
Bank Sta=5002.7,5006.7
Exp/Cntr=0.3,0.1

Type RM Length L Ch R = 1,10500,500,500,500
BEGIN DESCRIPTION:
SANFERNANDO024 21.0
END DESCRIPTION:
XS GIS Cut Line= 3
      2767405.69     10251303.12      2767040.83     10250368.63
      2766555.64     10250153.09
#Sta/Elev= 30
  3996.8 1217.18  4120.4 1211.53  4150.3 1211.08  4174.7 1209.68  4283.4 1206.33
  4313.3 1206.31  4329.6 1205.36  4392.1 1204.45  4506.1 1205.02  4590.3 1203.73
  4669.1 1199.72  4699.0 1199.10  4807.6 1194.58  4963.0 1190.08  4992.9 1187.76
  4993.2 1187.26  4996.7 1187.26  4996.9 1187.76  5016.6 1189.93  5076.0 1191.58
  5136.9 1194.20  5174.5 1194.83  5213.5 1196.27  5226.4 1197.35  5366.0 1202.46
  5371.5 1202.19  5394.7 1203.95  5509.0 1208.28  5516.5 1209.27  5530.9 1209.34
#Mann=3,-1,0
  3996.8    0.05       0  4992.9    0.03       0  4996.9    0.05       0
Bank Sta=4992.9,4996.9
Exp/Cntr=0.3,0.1

Type RM Length L Ch R = 1,10000,500,500,500
BEGIN DESCRIPTION:
SANFERNANDO024 20.0
END DESCRIPTION:
XS GIS Cut Line= 3
      2768105.67     10250453.10      2767307.82     10249967.71
      2766955.66     10249753.10
#Sta/Elev= 30
  4066.1 1211.10  4095.1 1211.21  4112.3 1209.47  4184.8 1206.97  4205.5 1206.91
  4226.9 1205.24  4241.7 1205.43  4269.5 1202.72  4307.6 1201.07  4422.6 1196.13
  4637.9 1188.65  4691.9 1186.49  4698.2 1185.04  4713.2 1184.45  4728.6 1186.56
  4733.2 1186.06  4829.4 1186.83  4918.5 1185.99  4976.6 1184.52  4990.8 1183.70
  4994.9 1182.50  4998.0 1181.15  4998.3 1180.65  5002.0 1181.15  5013.4 1181.35
  5034.7 1185.72  5084.4 1188.69  5224.5 1198.42  5267.1 1200.37  5412.4 1203.23
#Mann=10,-1,0
  4066.1    0.12       0  4112.3    0.05       0  4184.8    0.12       0
  4307.6    0.05       0  4637.9    0.12       0  4733.2    0.05       0
  4994.9    0.12       0  4998.0    0.07       0  5002.0    0.12       0
  5084.4    0.05       0
Bank Sta=4998,5002
Exp/Cntr=0.3,0.1

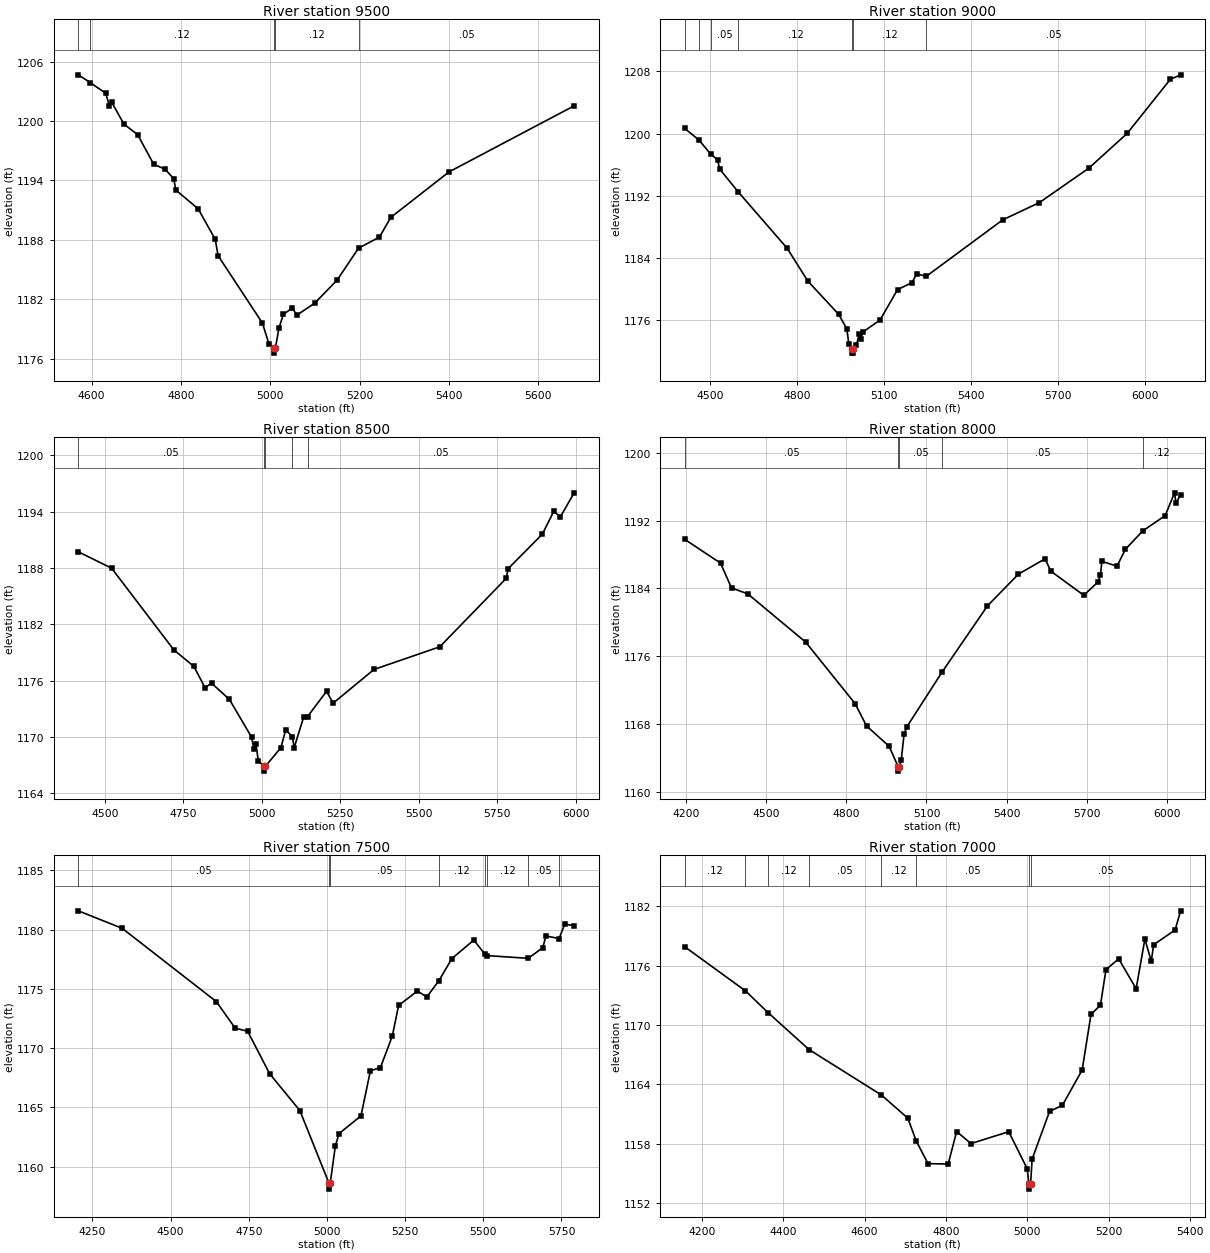
Type RM Length L Ch R = 1,9500,500,500,500
BEGIN DESCRIPTION:
SANFERNANDO024 19.0
END DESCRIPTION:
XS GIS Cut Line= 3
      2768055.70     10249703.12      2767635.12     10249614.12
      2766955.73     10249653.11
#Sta/Elev= 30
  4570.1 1204.67  4597.2 1203.87  4631.4 1202.81  4639.6 1201.55  4644.7 1201.91
  4672.3 1199.69  4703.0 1198.62  4739.0 1195.63  4764.3 1195.14  4783.6 1194.19
  4788.7 1193.02  4838.4 1191.14  4876.8 1188.04  4883.0 1186.41  4982.4 1179.59
  4997.2 1177.46  5007.4 1177.06  5007.7 1176.56  5011.4 1177.06  5019.5 1179.12
  5029.5 1180.50  5049.5 1181.11  5059.5 1180.40  5099.6 1181.61  5149.7 1183.94
  5197.6 1187.16  5244.5 1188.28  5269.9 1190.27  5400.1 1194.86  5680.5 1201.54
#Mann=5,-1,0
  4570.1    0.05       0  4597.2    0.12       0  5007.4    0.07       0
  5011.4    0.12       0  5197.6    0.05       0
Bank Sta=5007.4,5011.4
Exp/Cntr=0.3,0.1

Type RM Length L Ch R = 1,9000,500,500,500
BEGIN DESCRIPTION:
SANFERNANDO024 18.0
END DESCRIPTION:
XS GIS Cut Line= 3
      2768155.67     10249553.10      2767749.18     10249129.06
      2766755.72     10249653.09
#Sta/Elev= 30
  4412.6 1200.66  4461.3 1199.17  4501.7 1197.38  4525.6 1196.62  4532.9 1195.44
  4597.8 1192.46  4766.2 1185.23  4837.0 1181.03  4943.0 1176.77  4971.3 1174.91
  4978.5 1172.99  4990.6 1172.26  4990.9 1171.76  4994.4 1171.76  4994.6 1172.26
  5004.8 1172.77  5014.5 1174.28  5020.2 1173.60  5026.6 1174.47  5086.2 1176.02
  5146.6 1179.93  5196.3 1180.83  5212.7 1181.96  5245.6 1181.64  5509.7 1188.91
  5636.2 1191.13  5806.7 1195.56  5938.9 1200.03  6087.4 1206.97  6123.2 1207.56
#Mann=7,-1,0
  4412.6    0.05       0  4461.3    0.12       0  4501.7    0.05       0
  4597.8    0.12       0  4990.6    0.07       0  4994.6    0.12       0
  5245.6    0.05       0
Bank Sta=4990.6,4994.6
Exp/Cntr=0.3,0.1

Type RM Length L Ch R = 1,8500,500,500,500
BEGIN DESCRIPTION:
SANFERNANDO024 17.0
END DESCRIPTION:
XS GIS Cut Line= 3
      2768205.71     10249053.14      2767792.36     10248640.60
      2766955.72     10248103.13
#Sta/Elev= 30
  4416.0 1189.74  4522.1 1187.99  4720.1 1179.29  4783.7 1177.54  4819.1 1175.28
  4840.3 1175.74  4896.9 1174.02  4967.6 1169.99  4974.7 1168.71  4981.7 1169.22
  4988.8 1167.49  5007.2 1166.88  5007.5 1166.38  5011.2 1166.88  5060.8 1168.88
  5076.0 1170.76  5097.4 1170.06  5103.0 1168.87  5133.4 1172.15  5145.8 1172.19
  5206.1 1174.88  5227.2 1173.62  5357.3 1177.21  5566.6 1179.62  5778.1 1186.91
  5784.1 1187.94  5893.0 1191.61  5929.4 1194.04  5950.5 1193.46  5994.4 1196.02
#Mann=5,-1,0
  4416.0    0.05       0  5007.2    0.05       0  5011.2    0.05       0
  5097.4    0.12       0  5145.8    0.05       0
Bank Sta=5007.2,5011.2
Exp/Cntr=0.3,0.1

Type RM Length L Ch R = 1,8000,500,500,500
BEGIN DESCRIPTION:
SANFERNANDO024 16.0
END DESCRIPTION:
XS GIS Cut Line= 3
      2768205.69     10249003.12      2768021.30     10248220.75
      2767005.67     10247953.11
#Sta/Elev= 30
  4196.2 1189.79  4329.8 1186.99  4370.9 1184.06  4431.7 1183.36  4648.3 1177.66
  4833.3 1170.39  4875.7 1167.77  4960.4 1165.36  4994.2 1162.93  4994.5 1162.43
  4998.2 1162.93  5005.5 1163.71  5016.1 1166.78  5026.5 1167.66  5158.3 1174.13
  5327.9 1181.94  5443.7 1185.69  5543.6 1187.50  5564.6 1186.05  5688.3 1183.19
  5740.0 1184.73  5750.4 1185.56  5755.8 1187.20  5812.4 1186.63  5843.5 1188.61
  5908.2 1190.78  5992.4 1192.60  6027.6 1195.29  6032.7 1194.10  6050.3 1195.04
#Mann=5,-1,0
  4196.2    0.05       0  4994.2    0.07       0  4998.2    0.05       0
  5158.3    0.05       0  5908.2    0.12       0
Bank Sta=4994.2,4998.2
Exp/Cntr=0.3,0.1

Type RM Length L Ch R = 1,7500,500,500,500
BEGIN DESCRIPTION:
SANFERNANDO024 15.0
END DESCRIPTION:
XS GIS Cut Line= 3
      2768405.68     10248653.08      2768344.08     10247860.27
      2767555.65     10247803.11
#Sta/Elev= 30
  4204.8 1181.59  4345.2 1180.11  4646.1 1173.93  4706.3 1171.69  4746.4 1171.42
  4816.6 1167.84  4913.3 1164.73  5006.4 1158.60  5006.7 1158.10  5010.4 1158.60
  5026.7 1161.73  5038.5 1162.79  5108.7 1164.28  5138.8 1168.08  5171.0 1168.36
  5208.9 1171.02  5229.0 1173.60  5289.2 1174.82  5319.2 1174.32  5358.0 1175.69
  5399.4 1177.56  5469.6 1179.12  5505.6 1177.91  5512.6 1177.81  5643.5 1177.58
  5690.2 1178.48  5700.2 1179.47  5742.2 1179.25  5760.4 1180.46  5790.5 1180.34
#Mann=8,-1,0
  4204.8    0.05       0  5006.4    0.05       0  5010.4    0.05       0
  5358.0    0.12       0  5505.6    0.05       0  5512.6    0.12       0
  5643.5    0.05       0  5742.2    0.12       0
Bank Sta=5006.4,5010.4
Exp/Cntr=0.3,0.1

Type RM Length L Ch R = 1,7000,500,500,500
BEGIN DESCRIPTION:
SANFERNANDO024 14.0
END DESCRIPTION:
XS GIS Cut Line= 3
      2769355.66     10248053.09      2768696.85     10247528.43
      2768505.70     10247203.13
#Sta/Elev= 30
  4157.8 1177.92  4307.0 1173.46  4362.3 1171.27  4463.4 1167.52  4641.2 1162.93
  4706.3 1160.58  4726.7 1158.30  4756.0 1155.98  4805.6 1155.94  4826.4 1159.23
  4861.6 1158.01  4954.5 1159.21  5000.0 1155.46  5004.2 1153.90  5004.4 1153.40
  5008.2 1153.90  5012.1 1156.44  5055.0 1161.27  5086.3 1161.87  5135.1 1165.45
  5156.9 1171.09  5180.1 1172.01  5193.7 1175.62  5225.0 1176.70  5267.9 1173.68
  5289.4 1178.70  5305.1 1176.46  5310.9 1178.13  5363.7 1179.62  5377.3 1181.56
#Mann=8,-1,0
  4157.8    0.12       0  4307.0    0.05       0  4362.3    0.12       0
  4463.4    0.05       0  4641.2    0.12       0  4726.7    0.05       0
  5004.2    0.05       0  5008.2    0.05       0
Bank Sta=5004.2,5008.2
Exp/Cntr=0.3,0.1

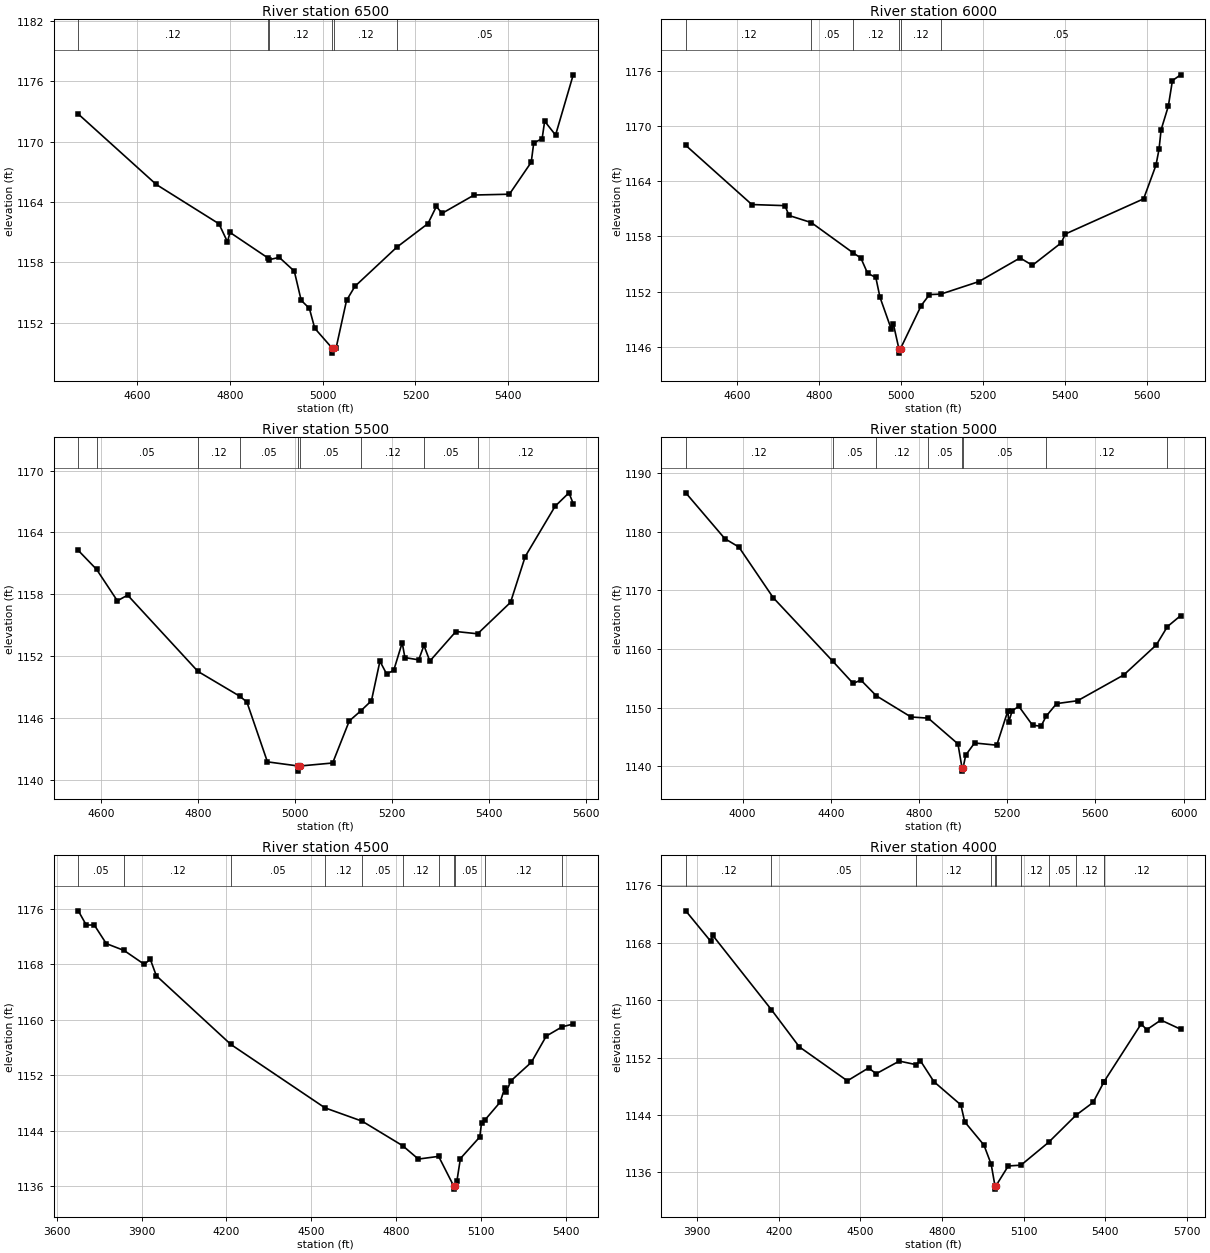
Type RM Length L Ch R = 1,6500,500,500,500
BEGIN DESCRIPTION:
SANFERNANDO024 13.0
END DESCRIPTION:
XS GIS Cut Line= 3
      2769355.68     10247853.11      2769152.23     10247366.53
      2768655.66     10247153.10
#Sta/Elev= 30
  4472.6 1172.75  4640.8 1165.75  4776.1 1161.84  4794.5 1160.04  4799.9 1160.98
  4882.5 1158.42  4884.4 1158.27  4906.2 1158.50  4938.7 1157.13  4953.5 1154.23
  4971.2 1153.43  4982.8 1151.45  5020.3 1149.48  5020.6 1148.98  5024.4 1149.48
  5028.9 1149.50  5051.4 1154.22  5069.5 1155.62  5159.8 1159.51  5227.1 1161.86
  5245.2 1163.56  5257.5 1162.88  5326.7 1164.70  5402.8 1164.78  5449.9 1167.96
  5455.3 1169.88  5473.4 1170.30  5478.9 1172.04  5502.4 1170.66  5540.5 1176.65
#Mann=6,-1,0
  4472.6    0.12       0  4882.5    0.05       0  4884.4    0.12       0
  5020.3    0.07       0  5024.4    0.12       0  5159.8    0.05       0
Bank Sta=5020.3,5024.4
Exp/Cntr=0.3,0.1

Type RM Length L Ch R = 1,6000,500,500,500
BEGIN DESCRIPTION:
SANFERNANDO024 12.0
END DESCRIPTION:
XS GIS Cut Line= 3
      2769905.64     10247103.11      2769385.13     10247035.35
      2768705.70     10247103.11
#Sta/Elev= 30
  4475.1 1167.88  4636.4 1161.45  4717.1 1161.33  4727.2 1160.26  4781.5 1159.49
  4883.3 1156.21  4902.4 1155.64  4918.8 1153.99  4938.9 1153.53  4949.0 1151.39
  4976.4 1147.94  4981.5 1148.52  4995.1 1145.81  4995.3 1145.31  4999.3 1145.81
  5049.7 1150.48  5069.8 1151.67  5097.6 1151.72  5190.4 1153.08  5290.9 1155.65
  5321.0 1154.85  5391.4 1157.29  5401.4 1158.25  5592.4 1162.07  5622.5 1165.72
  5630.0 1167.45  5635.0 1169.56  5652.7 1172.14  5662.7 1174.92  5682.8 1175.54
#Mann=6,-1,0
  4475.1    0.12       0  4781.5    0.05       0  4883.3    0.12       0
  4995.1    0.07       0  4999.3    0.12       0  5097.6    0.05       0
Bank Sta=4995.1,4999.3
Exp/Cntr=0.3,0.1

Type RM Length L Ch R = 1,5500,500,500,500
BEGIN DESCRIPTION:
SANFERNANDO024 11.0
END DESCRIPTION:
XS GIS Cut Line= 3
      2769655.69     10246803.11      2769276.88     10246564.31
      2768755.68     10246803.11
#Sta/Elev= 30
  4552.2 1162.25  4590.1 1160.40  4632.8 1157.36  4654.0 1157.91  4799.0 1150.51
  4885.0 1148.11  4900.0 1147.54  4942.4 1141.73  5005.8 1141.33  5006.1 1140.83
  5010.1 1141.33  5077.0 1141.62  5111.3 1145.70  5135.3 1146.69  5157.0 1147.66
  5174.5 1151.50  5188.3 1150.26  5203.0 1150.61  5220.5 1153.30  5226.0 1151.85
  5254.5 1151.63  5265.3 1153.03  5277.5 1151.51  5331.3 1154.38  5376.1 1154.16
  5444.0 1157.21  5474.3 1161.66  5536.0 1166.54  5564.5 1167.84  5573.3 1166.79
#Mann=9,-1,0
  4552.2    0.12       0  4590.1    0.05       0  4799.0    0.12       0
  4885.0    0.05       0  5005.8    0.03       0  5010.1    0.05       0
  5135.3    0.12       0  5265.3    0.05       0  5376.1    0.12       0
Bank Sta=5005.8,5010.1
Exp/Cntr=0.3,0.1

Type RM Length L Ch R = 1,5000,500,500,500
BEGIN DESCRIPTION:
SANFERNANDO024 10.0
END DESCRIPTION:
XS GIS Cut Line= 3
      2770455.65     10247203.07      2769637.67     10246248.11
      2768655.65     10246153.11
#Sta/Elev= 30
  3742.6 1186.64  3919.8 1178.83  3983.5 1177.40  4139.3 1168.76  4408.3 1157.97
  4501.6 1154.15  4536.7 1154.72  4606.7 1152.04  4763.9 1148.43  4842.1 1148.23
  4976.8 1143.84  4995.5 1139.70  4995.8 1139.20  4999.8 1139.70  5012.0 1141.93
  5052.2 1144.00  5152.7 1143.62  5202.8 1149.45  5207.8 1147.65  5223.0 1149.53
  5253.2 1150.23  5315.0 1147.02  5353.6 1146.86  5376.4 1148.55  5424.0 1150.71
  5519.3 1151.20  5728.7 1155.60  5876.1 1160.71  5926.4 1163.83  5986.6 1165.71
#Mann=8,-1,0
  3742.6    0.12       0  4408.3    0.05       0  4606.7    0.12       0
  4842.1    0.05       0  4995.5    0.05       0  4999.8    0.05       0
  5376.4    0.12       0  5926.4    0.05       0
Bank Sta=4995.5,4999.8
Exp/Cntr=0.3,0.1

Type RM Length L Ch R = 1,4500,500,500,500
BEGIN DESCRIPTION:
SANFERNANDO024 9.0
END DESCRIPTION:
XS GIS Cut Line= 3
      2770555.69     10246753.12      2769629.67     10245807.39
      2769255.72     10245603.13
#Sta/Elev= 30
  3676.4 1175.67  3704.6 1173.62  3732.9 1173.63  3775.3 1170.95  3838.2 1169.96
  3909.8 1167.96  3930.9 1168.70  3952.2 1166.32  4216.0 1156.41  4548.5 1147.28
  4679.9 1145.36  4823.4 1141.82  4878.6 1139.90  4950.3 1140.29  5002.9 1136.07
  5003.2 1135.57  5007.3 1136.07  5014.8 1136.70  5027.3 1139.98  5095.7 1143.08
  5102.1 1145.16  5114.3 1145.55  5167.6 1148.09  5183.7 1150.10  5189.4 1149.58
  5205.5 1151.16  5278.0 1153.84  5330.8 1157.62  5387.1 1158.96  5426.1 1159.36
#Mann=11,-1,0
  3676.4    0.05       0  3838.2    0.12       0  4216.0    0.05       0
  4548.5    0.12       0  4679.9    0.05       0  4823.4    0.12       0
  4950.3    0.05       0  5002.9    0.05       0  5007.3    0.05       0
  5114.3    0.12       0  5387.1    0.05       0
Bank Sta=5002.9,5007.3
Exp/Cntr=0.3,0.1

Type RM Length L Ch R = 1,4000,500,500,500
BEGIN DESCRIPTION:
SANFERNANDO024 8.0
END DESCRIPTION:
XS GIS Cut Line= 3
      2770855.71     10246453.14      2770057.27     10245636.23
      2769405.71     10245453.12
#Sta/Elev= 30
  3857.7 1172.46  3949.7 1168.20  3956.7 1169.05  4172.9 1158.66  4275.0 1153.50
  4451.7 1148.76  4529.5 1150.55  4557.8 1149.75  4642.6 1151.51  4702.4 1151.03
  4720.5 1151.54  4769.9 1148.64  4868.9 1145.40  4883.1 1143.04  4953.8 1139.80
  4980.4 1137.12  4994.0 1134.16  4994.3 1133.66  4998.4 1134.16  5043.2 1136.89
  5089.8 1137.00  5191.2 1140.18  5292.5 1143.98  5354.8 1145.74  5393.9 1148.54
  5394.7 1148.62  5531.4 1156.68  5552.4 1155.89  5604.1 1157.23  5676.8 1155.95
#Mann=11,-1,0
  3857.7    0.12       0  4172.9    0.05       0  4702.4    0.12       0
  4980.4    0.05       0  4994.0    0.05       0  4998.4    0.05       0
  5089.8    0.12       0  5191.2    0.05       0  5292.5    0.12       0
  5393.9    0.05       0  5394.7    0.12       0
Bank Sta=4994,4998.4
Exp/Cntr=0.3,0.1

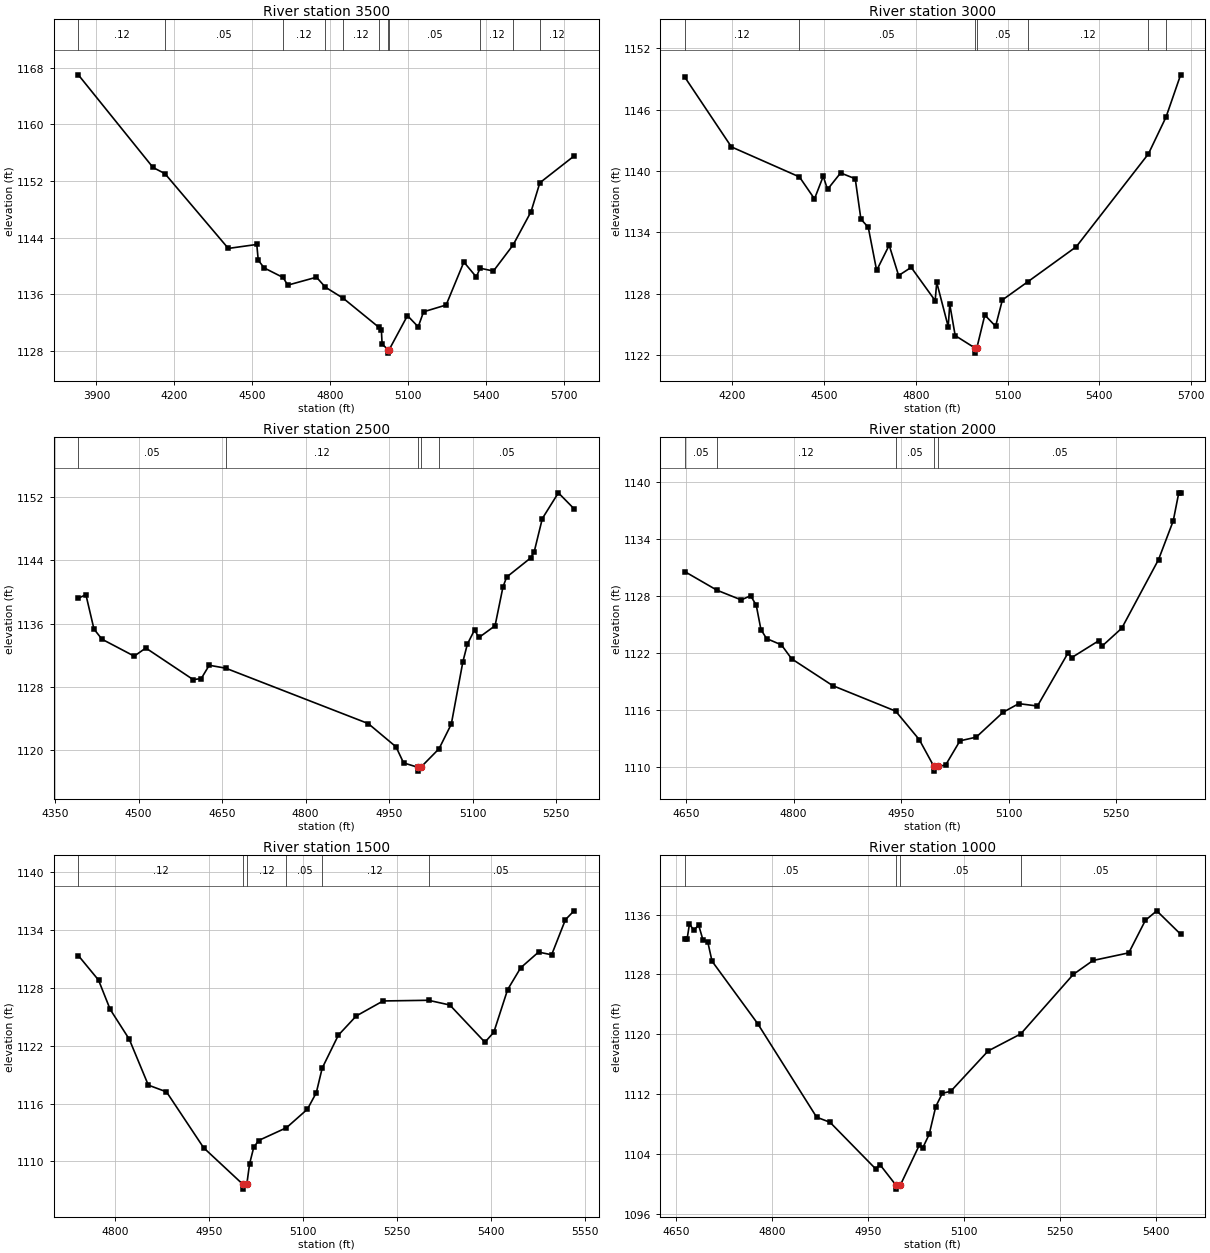
Type RM Length L Ch R = 1,3500,500,500,500
BEGIN DESCRIPTION:
SANFERNANDO024 7.0
END DESCRIPTION:
XS GIS Cut Line= 4
      2770905.68     10246203.10      2770437.58     10245331.73
      2770269.37     10245266.09      2769555.67     10245453.12
#Sta/Elev= 30
  3830.3 1166.97  4117.7 1153.90  4163.6 1153.03  4407.5 1142.48  4517.0 1143.04
  4522.7 1140.82  4545.4 1139.73  4618.3 1138.38  4636.2 1137.30  4746.8 1138.42
  4780.5 1137.03  4850.4 1135.43  4986.6 1131.36  4996.5 1131.00  4999.3 1128.98
  5022.2 1128.21  5022.5 1127.71  5026.7 1128.21  5096.9 1133.00  5138.2 1131.42
  5158.9 1133.54  5245.7 1134.50  5313.9 1140.56  5361.7 1138.46  5376.5 1139.69
  5427.7 1139.29  5503.1 1142.95  5572.4 1147.66  5606.3 1151.74  5737.8 1155.51
#Mann=11,-1,0
  3830.3    0.12       0  4163.6    0.05       0  4618.3    0.12       0
  4780.5    0.05       0  4850.4    0.12       0  4986.6    0.05       0
  5022.2    0.03       0  5026.7    0.05       0  5376.5    0.12       0
  5503.1    0.05       0  5606.3    0.12       0
Bank Sta=5022.2,5026.7
Exp/Cntr=0.3,0.1

Type RM Length L Ch R = 1,3000,500,500,500
BEGIN DESCRIPTION:
SANFERNANDO024 6.0
END DESCRIPTION:
XS GIS Cut Line= 3
      2770955.66     10245053.11      2770026.54     10244837.57
      2769605.69     10245353.10
#Sta/Elev= 30
  4046.2 1149.17  4198.0 1142.36  4420.2 1139.42  4469.4 1137.27  4497.9 1139.48
  4512.0 1138.20  4554.7 1139.81  4602.5 1139.24  4621.0 1135.29  4645.1 1134.48
  4672.4 1130.26  4713.4 1132.73  4744.2 1129.76  4785.3 1130.56  4863.6 1127.30
  4868.7 1129.09  4906.2 1124.76  4911.3 1126.94  4929.0 1123.88  4993.7 1122.66
  4994.2 1122.16  4999.7 1122.66  5025.8 1125.89  5061.0 1124.79  5083.2 1127.37
  5166.7 1129.16  5324.5 1132.58  5560.3 1141.68  5617.9 1145.29  5665.5 1149.42
#Mann=7,-1,0
  4046.2    0.12       0  4420.2    0.05       0  4993.7    0.03       0
  4999.7    0.05       0  5166.7    0.12       0  5560.3    0.05       0
  5617.9    0.12       0
Bank Sta=4993.7,4999.7
Exp/Cntr=0.3,0.1

Type RM Length L Ch R = 1,2500,500,500,500
BEGIN DESCRIPTION:
SANFERNANDO024 5.0
END DESCRIPTION:
XS GIS Cut Line= 3
      2770555.70     10244803.13      2770076.83     10244428.34
      2769855.65     10244253.08
#Sta/Elev= 30
  4391.9 1139.22  4405.5 1139.67  4420.0 1135.32  4434.4 1134.04  4492.3 1131.90
  4513.1 1132.93  4598.1 1128.94  4612.6 1129.06  4627.0 1130.75  4656.6 1130.38
  4912.6 1123.38  4962.5 1120.44  4976.1 1118.41  5001.1 1117.87  5001.6 1117.37
  5007.2 1117.87  5039.8 1120.20  5061.8 1123.31  5082.6 1131.19  5090.7 1133.43
  5103.5 1135.20  5111.5 1134.26  5140.4 1135.74  5154.6 1140.64  5161.2 1141.89
  5204.5 1144.32  5210.8 1145.12  5225.3 1149.29  5254.1 1152.54  5282.2 1150.53
#Mann=5,-1,0
  4391.9    0.05       0  4656.6    0.12       0  5001.1    0.07       0
  5007.2    0.12       0  5039.8    0.05       0
Bank Sta=5001.1,5007.2
Exp/Cntr=0.3,0.1

Type RM Length L Ch R = 1,2000,500,500,500
BEGIN DESCRIPTION:
SANFERNANDO024 4.0
END DESCRIPTION:
XS GIS Cut Line= 3
      2770655.71     10244303.13      2770386.82     10244076.43
      2770055.68     10244153.11
#Sta/Elev= 30
  4648.3 1130.55  4693.0 1128.60  4726.8 1127.58  4740.0 1128.02  4747.8 1127.01
  4754.3 1124.46  4762.1 1123.51  4782.9 1122.84  4797.2 1121.37  4854.4 1118.55
  4942.3 1115.86  4975.3 1112.85  4995.6 1110.04  4996.1 1109.54  5001.7 1110.04
  5012.0 1110.18  5032.0 1112.73  5054.7 1113.12  5092.3 1115.75  5114.1 1116.65
  5140.1 1116.40  5182.8 1121.99  5187.9 1121.50  5225.5 1123.27  5230.6 1122.73
  5257.8 1124.60  5309.1 1131.83  5329.6 1135.91  5337.3 1138.86  5339.9 1138.86
#Mann=5,-1,0
  4648.3    0.05       0  4693.0    0.12       0  4942.3    0.05       0
  4995.6    0.03       0  5001.7    0.05       0
Bank Sta=4995.6,5001.7
Exp/Cntr=0.3,0.1

Type RM Length L Ch R = 1,1500,500,500,500
BEGIN DESCRIPTION:
SANFERNANDO024 3.0
END DESCRIPTION:
XS GIS Cut Line= 3
      2770605.71     10243603.11      2770350.53     10243648.03
      2770005.68     10244053.12
#Sta/Elev= 30
  4740.9 1131.35  4773.1 1128.81  4791.7 1125.77  4822.2 1122.67  4852.6 1117.91
  4881.6 1117.21  4940.9 1111.41  5003.5 1107.62  5004.0 1107.12  5009.8 1107.62
  5014.2 1109.74  5020.8 1111.44  5028.5 1112.16  5073.1 1113.49  5106.5 1115.41
  5120.7 1117.12  5130.1 1119.67  5155.9 1123.09  5184.4 1125.08  5227.3 1126.64
  5299.8 1126.71  5333.8 1126.22  5389.8 1122.36  5404.0 1123.39  5426.0 1127.81
  5446.9 1130.08  5475.4 1131.71  5496.3 1131.43  5518.3 1135.07  5532.0 1135.99
#Mann=6,-1,0
  4740.9    0.12       0  5003.5    0.07       0  5009.8    0.12       0
  5073.1    0.05       0  5130.1    0.12       0  5299.8    0.05       0
Bank Sta=5003.5,5009.8
Exp/Cntr=0.3,0.1

Type RM Length L Ch R = 1,1000,500,500,500
BEGIN DESCRIPTION:
SANFERNANDO024 2.0
END DESCRIPTION:
XS GIS Cut Line= 3
      2770555.68     10243003.11      2770300.13     10243221.57
      2769871.93     10243315.58
#Sta/Elev= 30
  4663.8 1132.70  4667.1 1132.70  4670.9 1134.77  4677.5 1133.88  4685.2 1134.59
  4691.8 1132.65  4699.5 1132.33  4706.1 1129.77  4777.4 1121.42  4869.6 1108.90
  4890.5 1108.22  4961.8 1101.99  4968.4 1102.57  4993.8 1099.78  4994.3 1099.28
  5000.2 1099.78  5030.3 1105.21  5035.4 1104.79  5045.5 1106.62  5055.7 1110.31
  5066.0 1112.09  5079.2 1112.37  5137.6 1117.76  5188.6 1120.04  5270.7 1128.00
  5301.5 1129.86  5357.4 1130.88  5383.4 1135.24  5401.1 1136.50  5438.4 1133.37
#Mann=4,-1,0
  4663.8    0.05       0  4993.8    0.07       0  5000.2    0.05       0
  5188.6    0.05       0
Bank Sta=4993.8,5000.2
Exp/Cntr=0.3,0.1

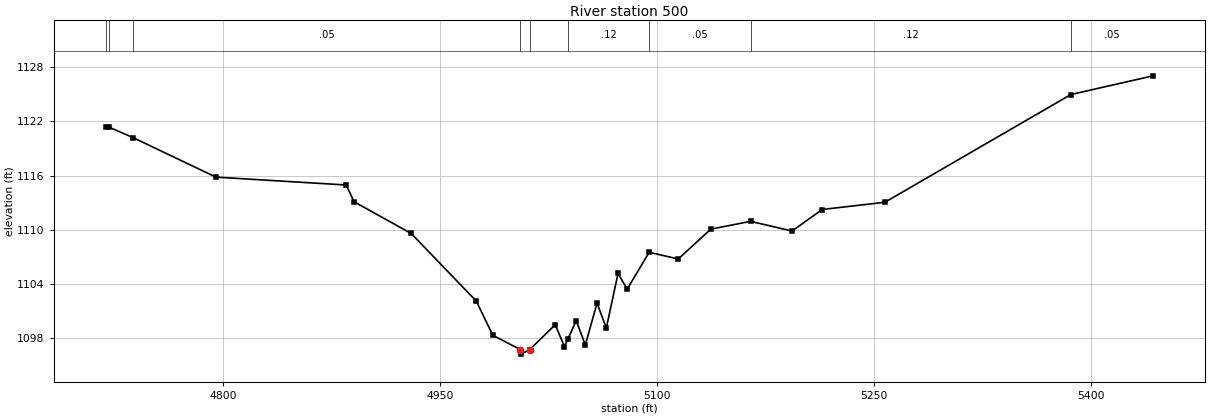
Type RM Length L Ch R = 1,500,0,0,0
BEGIN DESCRIPTION:
SANFERNANDO024 1.0
END DESCRIPTION:
XS GIS Cut Line= 3
      2770405.71     10242903.12      2770153.58     10242779.51
      2769805.68     10243053.12
#Sta/Elev= 30
  4719.2 1121.36  4721.3 1121.36  4738.2 1120.18  4795.2 1115.83  4885.2 1114.96
  4890.7 1113.10  4930.1 1109.60  4975.1 1102.12  4986.5 1098.34  5005.6 1096.76
  5006.1 1096.26  5012.0 1096.76  5029.6 1099.51  5036.0 1097.09  5038.4 1097.94
  5044.1 1099.97  5050.4 1097.28  5058.5 1101.89  5064.9 1099.14  5073.0 1105.18
  5079.3 1103.44  5094.5 1107.52  5114.6 1106.78  5137.1 1110.08  5164.6 1110.94
  5193.2 1109.87  5214.0 1112.25  5257.3 1113.05  5385.8 1124.96  5442.6 1127.03
#Mann=9,-1,0
  4719.2    0.05       0  4721.3    0.12       0  4738.2    0.05       0
  5005.6    0.05       0  5012.0    0.05       0  5038.4    0.12       0
  5094.5    0.05       0  5164.6    0.12       0  5385.8    0.05       0
Bank Sta=5005.6,5012
Exp/Cntr=0.3,0.1

Chan Stop Cuts=-1