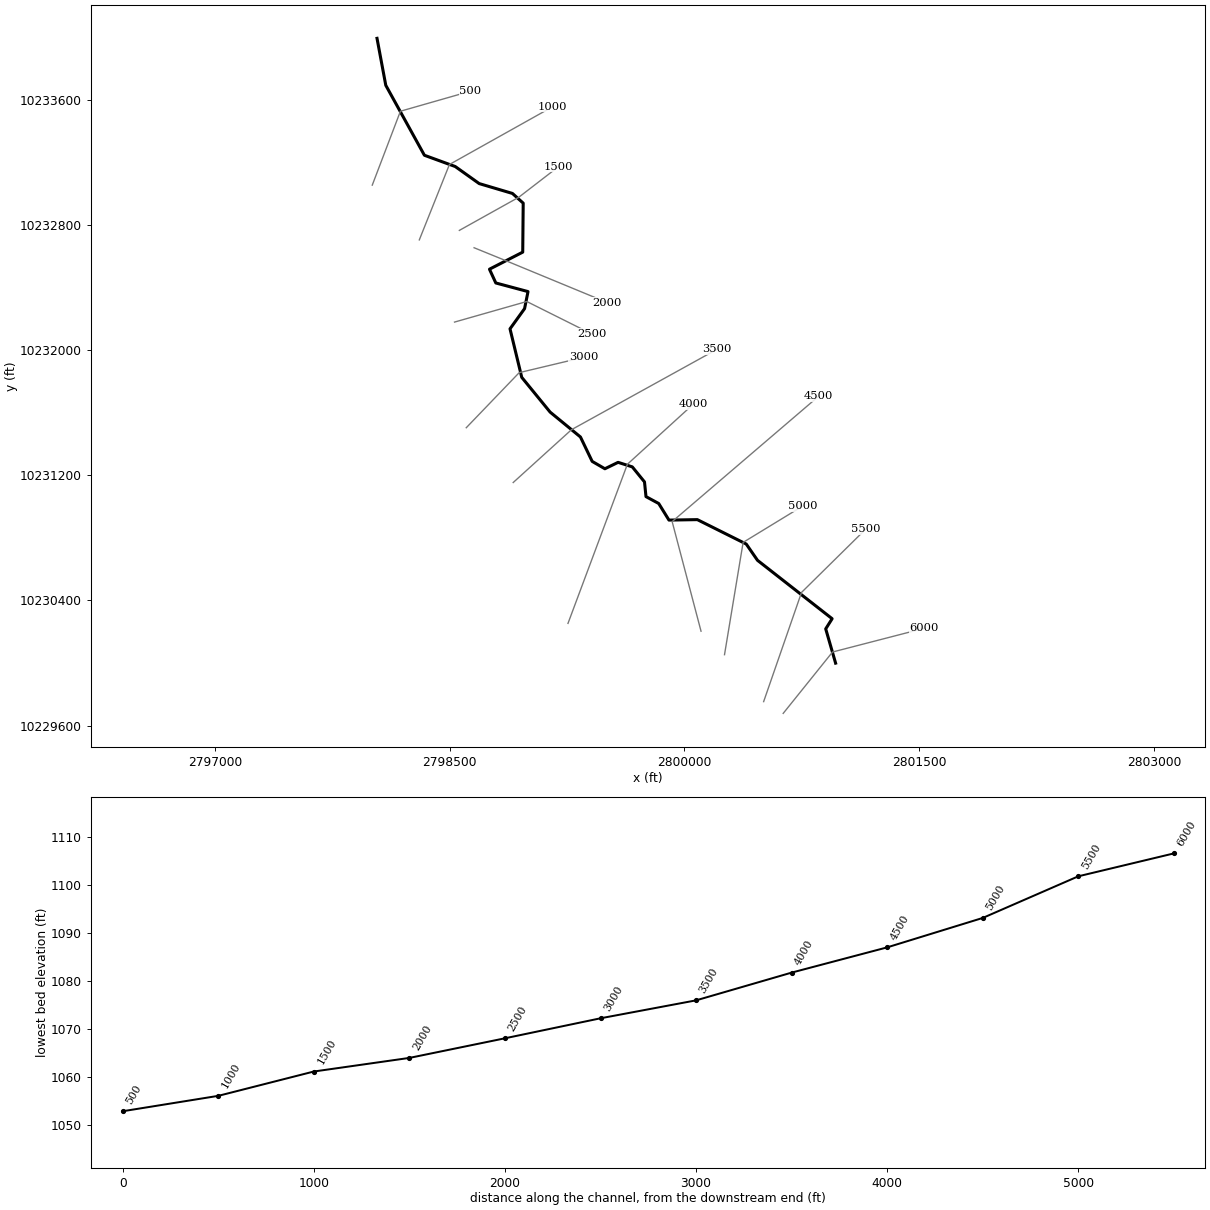
--- SANFERNANDO025.prj (project) ---

Proj Title=SANFERNANDO025 Base Level Engineering
Current Plan=p01
Default Exp/Contr=0.3,0.1
English Units
Geom File=g01
Flow File=f01
Plan File=p01
BEGIN DESCRIPTION:
SANFERNANDO025
END DESCRIPTION:

--- SANFERNANDO025.p01 (plan) ---

Plan Title=Multiple Run
Short Identifier=Multiple
Geom File=g01
Flow File=f01
Subcritical Flow
K Sum by GR= 0
Std Step Tol= 0.01
Critical Tol= 0.01
Num of Std Step Trials= 20
Max Error Tol= 0.3
Flow Tol Ratio= 0.001
Split Flow NTrial= 30
Split Flow Tol= 0.02
Split Flow Ratio= 0.02
Log Output Level= 0
Friction Slope Method= 1
Unsteady Friction Slope Method= 2
Unsteady Bridges Friction Slope Method= 1
Parabolic Critical Depth
Global Vel Dist=  1 , 1 , 1
Global Log Level= 0
CheckData=True
Encroach Param= -1, 0, 0, 0
BEGIN DESCRIPTION:
Multiple Run
END DESCRIPTION:

--- SANFERNANDO025.f01 (steady flow) ---

Flow Title=Multiple
Number of Profiles=7
Profile Names=10-year,25-year,50-year,1pct_min,100-year,1pct_plu,500-year
River Rch & RM= SANFERNANDO025,Reach-1,6000
     270     425     497     349     645    1194     884
Boundary for River Rch & Prof#=SANFERNANDO025,Reach-1,1
Up Type=0
Dn Type=3
Dn Slope=0.005
Boundary for River Rch & Prof#=SANFERNANDO025,Reach-1,2
Up Type=0
Dn Type=3
Dn Slope=0.005
Boundary for River Rch & Prof#=SANFERNANDO025,Reach-1,3
Up Type=0
Dn Type=3
Dn Slope=0.005
Boundary for River Rch & Prof#=SANFERNANDO025,Reach-1,4
Up Type=0
Dn Type=3
Dn Slope=0.005
Boundary for River Rch & Prof#=SANFERNANDO025,Reach-1,5
Up Type=0
Dn Type=3
Dn Slope=0.005
Boundary for River Rch & Prof#=SANFERNANDO025,Reach-1,6
Up Type=0
Dn Type=3
Dn Slope=0.005
Boundary for River Rch & Prof#=SANFERNANDO025,Reach-1,7
Up Type=0
Dn Type=3
Dn Slope=0.005

--- SANFERNANDO025.g01 (geometry) ---

Geom Title=Existing Conditions

River Reach=SANFERNANDO025,Reach-1
Reach XY= 30
      2800965.50     10229999.00      2800902.25     10230218.00
      2800943.25     10230283.00      2800466.50     10230656.00
      2800394.50     10230760.00      2800082.00     10230916.00
      2799900.75     10230913.00      2799835.25     10231019.00
      2799754.00     10231063.00      2799744.50     10231157.00
      2799666.50     10231253.00      2799575.75     10231282.00
      2799491.50     10231241.00      2799410.25     10231288.00
      2799335.25     10231444.00      2799141.50     10231603.00
      2798960.25     10231825.00      2798885.25     10232135.00
      2798978.25     10232264.00      2799000.25     10232373.00
      2798794.50     10232428.00      2798754.00     10232516.00
      2798966.50     10232625.00      2798969.50     10232938.00
      2798900.75     10233000.00      2798688.25     10233063.00
      2798535.25     10233172.00      2798338.25     10233244.00
      2798091.50     10233691.00      2798035.50     10233991.00

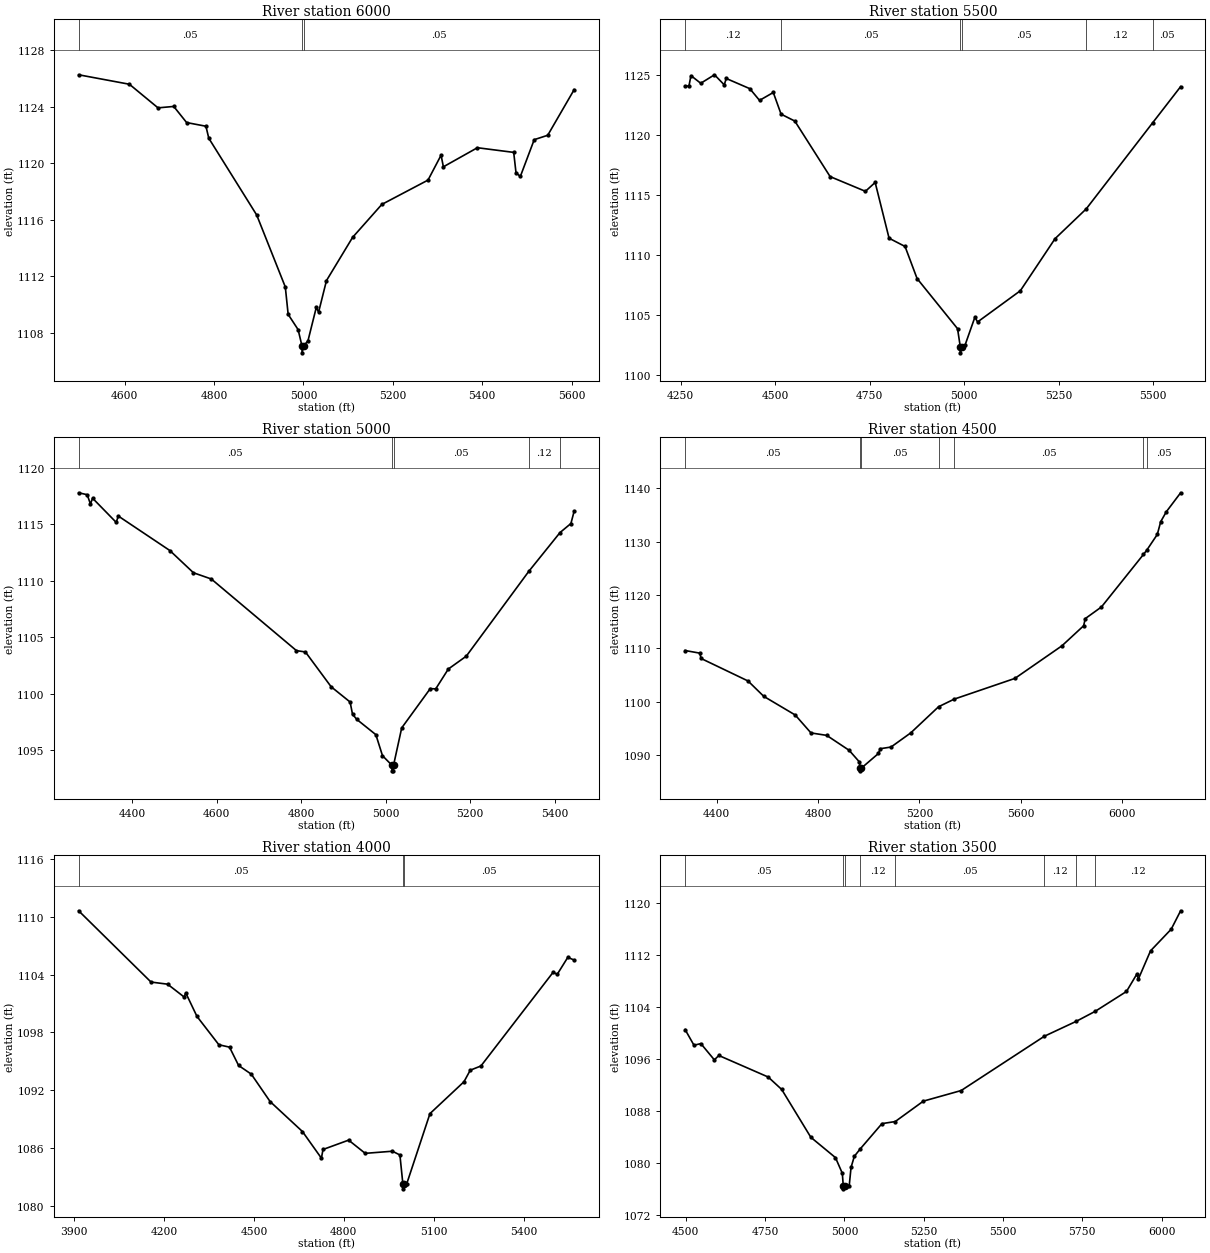
Type RM Length L Ch R = 1,6000,500,500,500
BEGIN DESCRIPTION:
SANFERNANDO025 12.0
END DESCRIPTION:
XS GIS Cut Line= 3
      2800630.70     10229678.14      2800945.77     10230070.11
      2801532.25     10230221.86
#Sta/Elev= 30
  4497.1 1126.25  4610.7 1125.58  4674.7 1123.91  4709.9 1124.01  4738.7 1122.87
  4781.9 1122.61  4788.3 1121.76  4895.5 1116.33  4959.5 1111.24  4965.9 1109.30
  4988.2 1108.22  4996.7 1107.08  4997.0 1106.58  5000.7 1107.08  5010.2 1107.43
  5028.8 1109.79  5034.0 1109.46  5051.6 1111.69  5110.1 1114.75  5175.5 1117.08
  5278.8 1118.80  5308.0 1120.56  5313.2 1119.74  5389.3 1121.09  5470.5 1120.76
  5475.7 1119.31  5485.4 1119.06  5516.4 1121.66  5546.6 1121.97  5605.8 1125.20
#Mann=3,-1,0
  4497.1    0.05       0  4996.7    0.03       0  5000.7    0.05       0
Bank Sta=4996.7,5000.7
Exp/Cntr=0.3,0.1

Type RM Length L Ch R = 1,5500,500,500,500
BEGIN DESCRIPTION:
SANFERNANDO025 11.0
END DESCRIPTION:
XS GIS Cut Line= 3
      2800505.70     10229753.16      2800747.78     10230450.96
      2801155.68     10230853.10
#Sta/Elev= 30
  4261.4 1124.11  4271.6 1124.12  4276.9 1124.99  4302.8 1124.35  4339.2 1125.06
  4365.0 1124.22  4370.3 1124.75  4432.6 1123.90  4458.4 1122.92  4494.8 1123.58
  4515.4 1121.77  4551.8 1121.19  4645.2 1116.55  4738.6 1115.32  4764.4 1116.06
  4801.2 1111.40  4843.5 1110.71  4875.3 1108.03  4982.4 1103.84  4989.7 1102.32
  4989.9 1101.82  4993.7 1102.32  5002.0 1102.44  5028.3 1104.80  5035.4 1104.40
  5148.6 1107.01  5240.4 1111.36  5322.9 1113.85  5498.8 1121.05  5572.8 1124.07
#Mann=6,-1,0
  4261.4    0.12       0  4515.4    0.05       0  4989.7    0.03       0
  4993.7    0.05       0  5322.9    0.12       0  5498.8    0.05       0
Bank Sta=4989.7,4993.7
Exp/Cntr=0.3,0.1

Type RM Length L Ch R = 1,5000,500,500,500
BEGIN DESCRIPTION:
SANFERNANDO025 10.0
END DESCRIPTION:
XS GIS Cut Line= 3
      2800255.68     10230053.10      2800374.57     10230770.51
      2800755.69     10231003.12
#Sta/Elev= 30
  4272.8 1117.77  4293.1 1117.60  4300.8 1116.77  4305.8 1117.29  4361.8 1115.15
  4366.8 1115.71  4488.8 1112.66  4544.8 1110.69  4587.0 1110.14  4788.7 1103.80
  4810.0 1103.68  4870.9 1100.60  4915.8 1099.25  4921.5 1098.17  4931.7 1097.71
  4976.8 1096.36  4992.5 1094.50  5014.7 1093.66  5015.0 1093.16  5018.5 1093.16
  5018.7 1093.66  5038.0 1096.96  5105.7 1100.44  5118.5 1100.41  5148.4 1102.17
  5191.0 1103.31  5338.9 1110.81  5413.0 1114.25  5438.8 1115.05  5446.5 1116.15
#Mann=5,-1,0
  4272.8    0.05       0  5014.7    0.05       0  5018.7    0.05       0
  5338.9    0.12       0  5413.0    0.05       0
Bank Sta=5014.7,5018.7
Exp/Cntr=0.3,0.1

Type RM Length L Ch R = 1,4500,500,500,500
BEGIN DESCRIPTION:
SANFERNANDO025 9.0
END DESCRIPTION:
XS GIS Cut Line= 3
      2800105.68     10230203.12      2799921.15     10230903.41
      2800855.69     10231703.12
#Sta/Elev= 30
  4275.8 1109.60  4333.7 1109.11  4338.8 1108.11  4524.0 1103.89  4586.0 1101.01
  4710.1 1097.51  4772.2 1094.15  4834.2 1093.69  4922.7 1090.89  4963.0 1088.72
  4966.7 1087.54  4966.9 1087.04  4970.7 1087.54  5038.4 1090.30  5045.5 1091.19
  5087.8 1091.50  5165.8 1094.16  5275.4 1099.06  5337.2 1100.49  5576.3 1104.37
  5761.8 1110.48  5847.4 1114.24  5854.0 1115.59  5917.7 1117.77  6083.3 1127.61
  6096.3 1128.41  6137.9 1131.36  6151.5 1133.77  6173.5 1135.62  6230.0 1139.18
#Mann=7,-1,0
  4275.8    0.05       0  4966.7    0.03       0  4970.7    0.05       0
  5275.4    0.12       0  5337.2    0.05       0  6083.3    0.12       0
  6096.3    0.05       0
Bank Sta=4966.7,4970.7
Exp/Cntr=0.3,0.1

Type RM Length L Ch R = 1,4000,500,500,500
BEGIN DESCRIPTION:
SANFERNANDO025 8.0
END DESCRIPTION:
XS GIS Cut Line= 3
      2799255.68     10230253.10      2799635.24     10231269.87
      2800055.68     10231653.11
#Sta/Elev= 30
  3914.7 1110.62  4156.3 1103.23  4211.6 1103.01  4266.9 1101.68  4272.2 1102.11
  4309.7 1099.67  4382.8 1096.73  4418.4 1096.48  4448.7 1094.58  4491.1 1093.68
  4553.9 1090.84  4661.9 1087.73  4725.1 1084.97  4730.5 1085.87  4816.0 1086.84
  4871.3 1085.47  4962.2 1085.69  4987.2 1085.30  4997.1 1082.29  4997.3 1081.79
  5001.1 1082.29  5009.8 1082.30  5087.5 1089.59  5201.0 1092.89  5222.0 1094.09
  5257.7 1094.53  5498.3 1104.23  5512.5 1104.04  5547.6 1105.79  5568.9 1105.51
#Mann=3,-1,0
  3914.7    0.05       0  4997.1    0.03       0  5001.1    0.05       0
Bank Sta=4997.1,5001.1
Exp/Cntr=0.3,0.1

Type RM Length L Ch R = 1,3500,500,500,500
BEGIN DESCRIPTION:
SANFERNANDO025 7.0
END DESCRIPTION:
XS GIS Cut Line= 3
      2798905.69     10231153.12      2799277.92     10231490.53
      2800205.65     10232003.09
#Sta/Elev= 30
  4497.6 1100.52  4525.6 1098.11  4547.3 1098.36  4589.8 1095.86  4604.0 1096.53
  4759.5 1093.22  4802.1 1091.31  4894.0 1083.95  4971.7 1080.82  4993.3 1078.41
  4996.2 1076.52  4996.4 1076.02  5000.2 1076.52  5015.1 1076.53  5020.8 1079.32
  5031.2 1081.03  5049.9 1082.17  5118.2 1086.05  5160.1 1086.37  5248.8 1089.51
  5368.0 1091.14  5630.6 1099.50  5730.6 1101.78  5790.1 1103.31  5889.2 1106.38
  5921.3 1109.01  5927.0 1108.33  5964.9 1112.62  6030.2 1115.96  6059.9 1118.79
#Mann=8,-1,0
  4497.6    0.05       0  4996.2    0.05       0  5000.2    0.05       0
  5049.9    0.12       0  5160.1    0.05       0  5630.6    0.12       0
  5730.6    0.05       0  5790.1    0.12       0
Bank Sta=4996.2,5000.2
Exp/Cntr=0.3,0.1

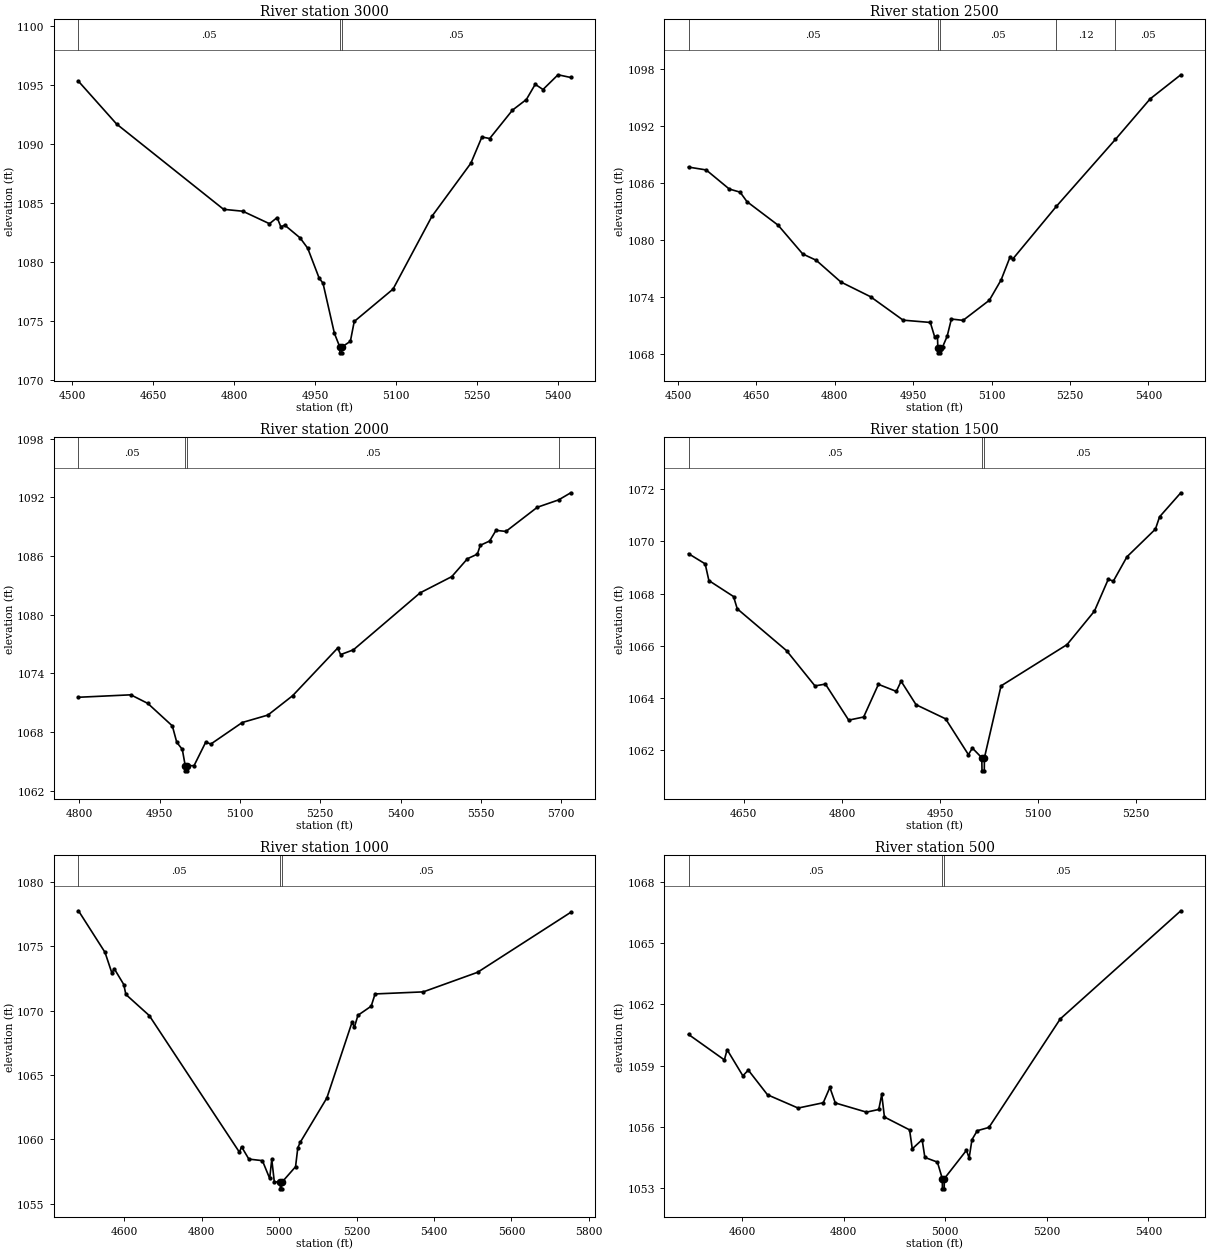
Type RM Length L Ch R = 1,3000,500,500,500
BEGIN DESCRIPTION:
SANFERNANDO025 6.0
END DESCRIPTION:
XS GIS Cut Line= 3
      2798605.69     10231503.12      2798943.91     10231855.03
      2799355.69     10231953.11
#Sta/Elev= 30
  4511.9 1095.34  4582.5 1091.71  4780.6 1084.47  4816.1 1084.31  4865.5 1083.25
  4879.7 1083.77  4886.6 1082.98  4893.8 1083.13  4922.1 1082.05  4936.3 1081.17
  4957.4 1078.64  4964.6 1078.20  4985.7 1073.95  4995.7 1072.79  4995.9 1072.29
  4999.4 1072.29  4999.7 1072.79  5015.3 1073.27  5022.4 1074.95  5094.3 1077.70
  5166.3 1083.88  5238.3 1088.38  5258.8 1090.61  5273.2 1090.48  5315.4 1092.89
  5341.1 1093.79  5357.5 1095.08  5371.9 1094.64  5399.7 1095.89  5423.3 1095.66
#Mann=3,-1,0
  4511.9    0.05       0  4995.7    0.03       0  4999.7    0.05       0
Bank Sta=4995.7,4999.7
Exp/Cntr=0.3,0.1

Type RM Length L Ch R = 1,2500,500,500,500
BEGIN DESCRIPTION:
SANFERNANDO025 5.0
END DESCRIPTION:
XS GIS Cut Line= 3
      2798530.73     10232178.12      2798992.27     10232309.59
      2799405.68     10232103.11
#Sta/Elev= 30
  4520.1 1087.69  4553.9 1087.39  4598.1 1085.38  4618.8 1085.05  4632.0 1084.05
  4691.6 1081.57  4738.7 1078.54  4764.4 1077.88  4811.6 1075.59  4868.4 1074.04
  4930.8 1071.57  4982.8 1071.33  4991.3 1069.78  4996.5 1069.93  4997.2 1068.63
  4997.4 1068.13  5000.9 1068.13  5001.2 1068.63  5006.4 1068.77  5015.0 1069.87
  5023.1 1071.69  5045.5 1071.55  5095.8 1073.67  5118.2 1075.80  5135.0 1078.17
  5140.6 1078.01  5224.1 1083.56  5336.9 1090.60  5403.4 1094.87  5462.1 1097.41
#Mann=5,-1,0
  4520.1    0.05       0  4997.2    0.03       0  5001.2    0.05       0
  5224.1    0.12       0  5336.9    0.05       0
Bank Sta=4997.2,5001.2
Exp/Cntr=0.3,0.1

Type RM Length L Ch R = 1,2000,500,500,500
BEGIN DESCRIPTION:
SANFERNANDO025 4.0
END DESCRIPTION:
XS GIS Cut Line= 3
      2798655.70     10232653.10      2798842.24     10232577.18
      2799505.66     10232303.12
#Sta/Elev= 30
  4798.6 1071.57  4896.3 1071.82  4928.1 1070.94  4973.9 1068.64  4982.1 1066.97
  4992.5 1066.24  4998.0 1064.55  4998.2 1064.05  5001.7 1064.05  5002.0 1064.55
  5014.5 1064.59  5036.2 1066.98  5045.8 1066.79  5104.4 1068.99  5152.3 1069.75
  5198.5 1071.73  5282.6 1076.60  5288.1 1075.93  5312.0 1076.42  5436.5 1082.24
  5495.6 1083.90  5524.9 1085.73  5543.4 1086.20  5548.8 1087.10  5566.3 1087.54
  5578.2 1088.63  5596.7 1088.52  5655.3 1090.99  5695.0 1091.74  5717.8 1092.47
#Mann=4,-1,0
  4798.6    0.05       0  4998.0    0.05       0  5002.0    0.05       0
  5695.0    0.12       0
Bank Sta=4998,5002
Exp/Cntr=0.3,0.1

Type RM Length L Ch R = 1,1500,500,500,500
BEGIN DESCRIPTION:
SANFERNANDO025 3.0
END DESCRIPTION:
XS GIS Cut Line= 3
      2798561.61     10232763.94      2798941.24     10232975.69
      2799193.64     10233170.13
#Sta/Elev= 30
  4565.3 1069.53  4590.8 1069.14  4596.5 1068.50  4634.2 1067.89  4639.9 1067.42
  4715.3 1065.82  4758.8 1064.47  4774.8 1064.54  4810.4 1063.16  4833.3 1063.28
  4855.9 1064.53  4883.3 1064.26  4890.6 1064.65  4913.5 1063.75  4958.7 1063.21
  4993.6 1061.84  4999.7 1062.09  5014.1 1061.72  5014.4 1061.22  5017.9 1061.22
  5018.1 1061.72  5043.5 1064.47  5144.5 1066.05  5186.4 1067.33  5207.6 1068.55
  5215.4 1068.48  5236.2 1069.41  5279.8 1070.47  5286.1 1070.94  5318.6 1071.86
#Mann=3,-1,0
  4565.3    0.05       0  5014.1    0.03       0  5018.1    0.05       0
Bank Sta=5014.1,5018.1
Exp/Cntr=0.3,0.1

Type RM Length L Ch R = 1,1000,500,500,500
BEGIN DESCRIPTION:
SANFERNANDO025 2.0
END DESCRIPTION:
XS GIS Cut Line= 3
      2798305.70     10232703.15      2798498.24     10233185.00
      2799155.70     10233553.12
#Sta/Elev= 30
  4481.1 1077.76  4549.7 1074.53  4567.2 1072.95  4574.0 1073.24  4598.2 1072.03
  4603.6 1071.26  4664.1 1069.62  4897.2 1059.00  4902.6 1059.43  4921.5 1058.47
  4956.5 1058.35  4975.3 1056.97  4980.7 1058.45  4987.2 1056.72  5002.6 1056.66
  5002.8 1056.16  5006.3 1056.16  5006.6 1056.66  5042.2 1057.88  5048.0 1059.35
  5054.4 1059.78  5123.1 1063.22  5188.4 1069.12  5194.1 1068.70  5203.4 1069.64
  5237.7 1070.35  5247.7 1071.30  5372.2 1071.46  5512.6 1072.98  5753.5 1077.64
#Mann=3,-1,0
  4481.1    0.05       0  5002.6    0.03       0  5006.6    0.05       0
Bank Sta=5002.6,5006.6
Exp/Cntr=0.3,0.1

Type RM Length L Ch R = 1,500,0,0,0
BEGIN DESCRIPTION:
SANFERNANDO025 1.0
END DESCRIPTION:
XS GIS Cut Line= 3
      2798005.17     10233053.11      2798185.08     10233525.30
      2798630.82     10233652.75
#Sta/Elev= 30
  4494.7 1060.53  4565.3 1059.28  4570.7 1059.78  4601.7 1058.50  4612.4 1058.78
  4650.2 1057.57  4710.4 1056.92  4759.9 1057.18  4772.9 1057.93  4783.6 1057.17
  4844.9 1056.72  4869.2 1056.85  4875.0 1057.59  4880.3 1056.48  4929.8 1055.85
  4935.1 1054.92  4954.5 1055.37  4959.9 1054.50  4984.6 1054.27  4994.2 1053.46
  4994.4 1052.96  4997.9 1052.96  4998.2 1053.46  5041.8 1054.85  5047.0 1054.47
  5052.6 1055.37  5063.0 1055.81  5086.0 1055.97  5226.4 1061.29  5463.6 1066.59
#Mann=3,-1,0
  4494.7    0.05       0  4994.2    0.03       0  4998.2    0.05       0
Bank Sta=4994.2,4998.2
Exp/Cntr=0.3,0.1

Chan Stop Cuts=-1