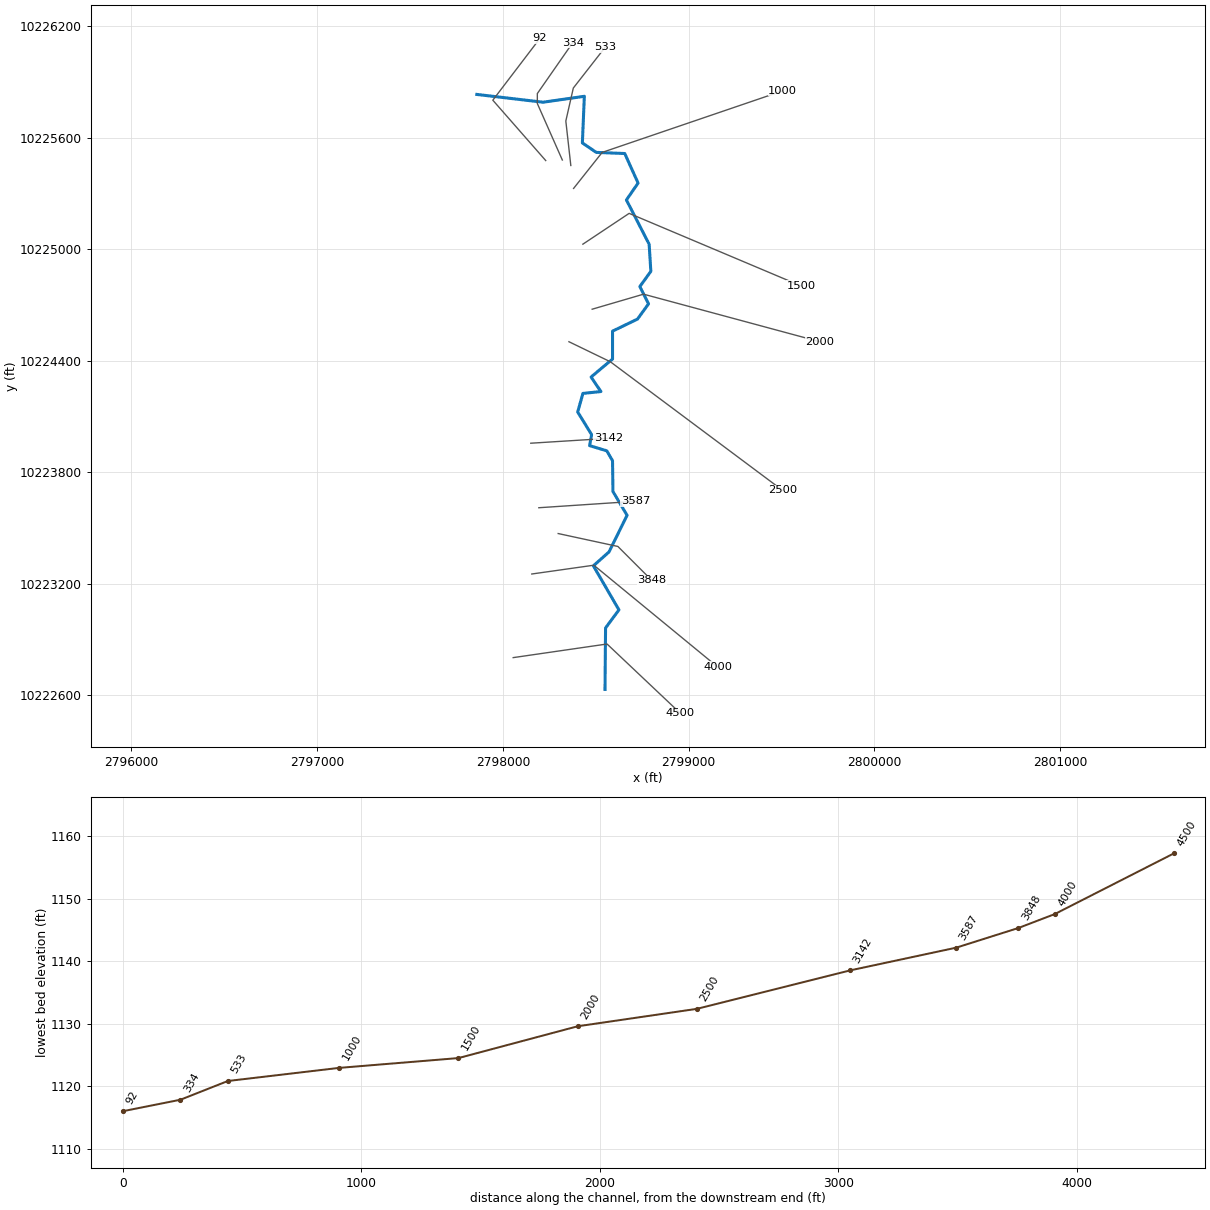
--- SANFERNANDO026.prj (project) ---

Proj Title=SANFERNANDO026 Base Level Engineering
Current Plan=p01
Default Exp/Contr=0.3,0.1
English Units
Geom File=g01
Flow File=f01
Plan File=p01
BEGIN DESCRIPTION:
SANFERNANDO026
END DESCRIPTION:

--- SANFERNANDO026.p01 (plan) ---

Plan Title=Multiple Run
Short Identifier=Multiple
Geom File=g01
Flow File=f01
Subcritical Flow
K Sum by GR= 0
Std Step Tol= 0.01
Critical Tol= 0.01
Num of Std Step Trials= 20
Max Error Tol= 0.3
Flow Tol Ratio= 0.001
Split Flow NTrial= 30
Split Flow Tol= 0.02
Split Flow Ratio= 0.02
Log Output Level= 0
Friction Slope Method= 1
Unsteady Friction Slope Method= 2
Unsteady Bridges Friction Slope Method= 1
Parabolic Critical Depth
Global Vel Dist=  1 , 1 , 1
Global Log Level= 0
CheckData=True
Encroach Param= -1, 0, 0, 0
BEGIN DESCRIPTION:
Multiple Run
END DESCRIPTION:

--- SANFERNANDO026.f01 (steady flow) ---

Flow Title=Multiple
Number of Profiles=7
Profile Names=10-year,25-year,50-year,1pct_min,100-year,1pct_plu,500-year
River Rch & RM= SANFERNANDO026,Reach-1,4500
     223     346     465     306     609    1212     849
River Rch & RM= SANFERNANDO026,Reach-1,334
     415     668     967     565    1296    2969    1791
Boundary for River Rch & Prof#=SANFERNANDO026,Reach-1,1
Up Type=0
Dn Type=3
Dn Slope=0.005
Boundary for River Rch & Prof#=SANFERNANDO026,Reach-1,2
Up Type=0
Dn Type=3
Dn Slope=0.005
Boundary for River Rch & Prof#=SANFERNANDO026,Reach-1,3
Up Type=0
Dn Type=3
Dn Slope=0.005
Boundary for River Rch & Prof#=SANFERNANDO026,Reach-1,4
Up Type=0
Dn Type=3
Dn Slope=0.005
Boundary for River Rch & Prof#=SANFERNANDO026,Reach-1,5
Up Type=0
Dn Type=3
Dn Slope=0.005
Boundary for River Rch & Prof#=SANFERNANDO026,Reach-1,6
Up Type=0
Dn Type=3
Dn Slope=0.005
Boundary for River Rch & Prof#=SANFERNANDO026,Reach-1,7
Up Type=0
Dn Type=3
Dn Slope=0.005

--- SANFERNANDO026.g01 (geometry) ---

Geom Title=Existing Conditions

River Reach=SANFERNANDO026,Reach-1
Reach XY= 30
      2798549.75     10222632.00      2798552.75     10222963.00
      2798624.75     10223060.00      2798487.25     10223297.00
      2798571.50     10223372.00      2798668.50     10223569.00
      2798592.50     10223697.00      2798590.25     10223863.00
      2798559.25     10223916.00      2798466.75     10223944.00
      2798477.75     10224003.00      2798402.75     10224125.00
      2798431.00     10224225.00      2798527.75     10224235.00
      2798474.75     10224313.00      2798590.25     10224410.00
      2798590.25     10224560.00      2798724.75     10224625.00
      2798784.00     10224707.00      2798737.25     10224800.00
      2798796.50     10224882.00      2798787.25     10225028.00
      2798665.00     10225266.00      2798727.75     10225357.00
      2798656.00     10225516.00      2798502.75     10225522.00
      2798428.00     10225573.00      2798438.50     10225824.00
      2798216.75     10225792.00      2797859.75     10225834.00

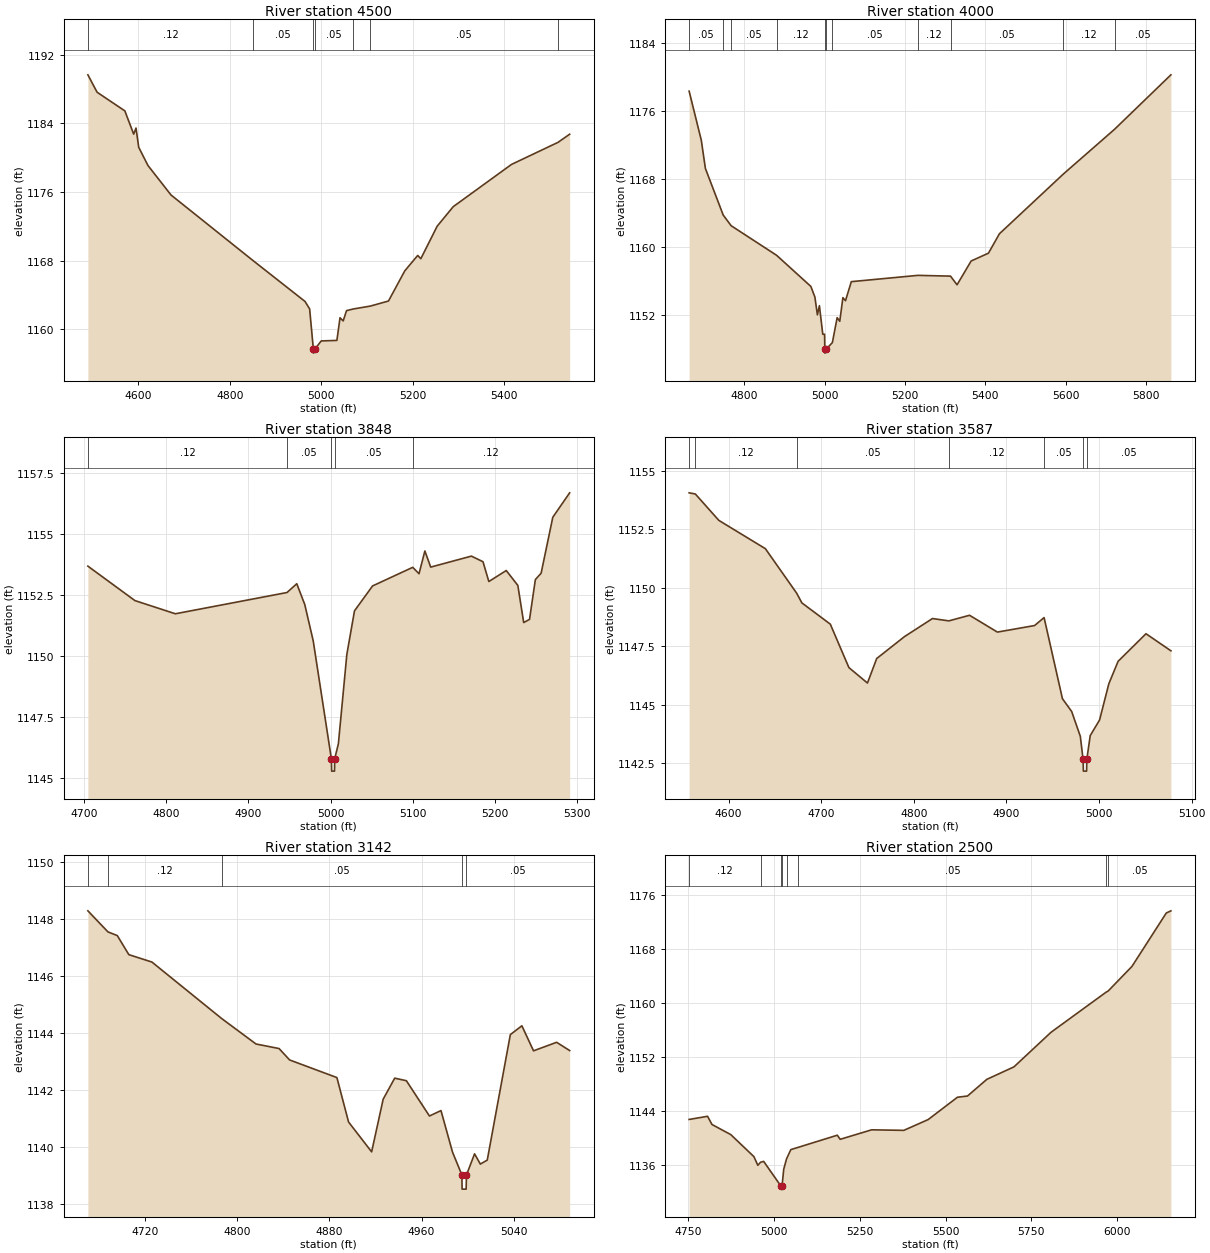
Type RM Length L Ch R = 1,4500,500,500,500
BEGIN DESCRIPTION:
SANFERNANDO026 9.0
END DESCRIPTION:
XS GIS Cut Line= 3
      2798055.65     10222803.11      2798560.75     10222876.44
      2798955.71     10222503.08
#Sta/Elev= 30
  4489.6 1189.66  4509.8 1187.63  4570.5 1185.46  4589.8 1182.75  4594.9 1183.46
  4600.8 1181.22  4621.0 1179.10  4671.5 1175.66  4850.7 1168.03  4964.6 1163.26
  4974.7 1162.39  4982.8 1157.74  4983.0 1157.24  4986.8 1157.74  5000.0 1158.66
  5034.3 1158.72  5041.2 1161.36  5048.1 1160.99  5055.4 1162.19  5070.0 1162.38
  5107.5 1162.72  5147.2 1163.31  5182.8 1166.82  5211.1 1168.62  5218.0 1168.24
  5253.6 1172.02  5288.8 1174.30  5416.2 1179.22  5517.9 1181.79  5543.5 1182.74
#Mann=7,-1,0
  4489.6    0.12       0  4850.7    0.05       0  4982.8    0.05       0
  4986.8    0.05       0  5070.0    0.12       0  5107.5    0.05       0
  5517.9    0.12       0
Bank Sta=4982.8,4986.8
Exp/Cntr=0.3,0.1

Type RM Length L Ch R = 1,4000,152,152,152
BEGIN DESCRIPTION:
SANFERNANDO026 8.0
END DESCRIPTION:
XS GIS Cut Line= 3
      2798155.68     10223253.11      2798489.54     10223300.47
      2799155.70     10222753.10
#Sta/Elev= 30
  4662.8 1178.31  4693.1 1172.54  4703.3 1169.22  4747.6 1163.75  4767.3 1162.50
  4880.5 1159.02  4965.8 1155.36  4975.9 1154.11  4982.1 1152.02  4987.1 1153.10
  4995.5 1149.74  5000.0 1149.74  5000.6 1148.02  5000.8 1147.52  5004.6 1148.02
  5019.4 1148.76  5031.3 1151.69  5037.8 1151.26  5045.6 1154.04  5052.1 1153.68
  5066.5 1155.92  5232.3 1156.66  5313.5 1156.57  5329.8 1155.55  5364.9 1158.35
  5408.0 1159.27  5435.3 1161.55  5594.2 1168.56  5721.9 1173.83  5862.2 1180.23
#Mann=11,-1,0
  4662.8    0.05       0  4747.6    0.12       0  4767.3    0.05       0
  4880.5    0.12       0  5000.6    0.07       0  5004.6    0.12       0
  5019.4    0.05       0  5232.3    0.12       0  5313.5    0.05       0
  5594.2    0.12       0  5721.9    0.05       0
Bank Sta=5000.6,5004.6
Exp/Cntr=0.3,0.1

Type RM Length L Ch R = 1,3848,261,261,261
BEGIN DESCRIPTION:
Mapping XS 6c1accd7
END DESCRIPTION:
XS GIS Cut Line= 3
      2798297.82     10223470.84      2798619.00     10223401.40
      2798801.01     10223219.39
#Sta/Elev= 30
  4704.8 1153.69  4762.0 1152.28  4811.2 1151.74  4947.0 1152.61  4958.9 1152.97
  4968.6 1152.12  4978.9 1150.63  5001.0 1145.80  5001.3 1145.30  5004.8 1145.30
  5005.0 1145.80  5009.5 1146.42  5019.8 1150.08  5029.1 1151.86  5051.1 1152.88
  5099.9 1153.64  5107.6 1153.38  5114.7 1154.31  5121.8 1153.65  5171.3 1154.10
  5185.4 1153.87  5192.5 1153.06  5213.7 1153.51  5227.8 1152.90  5234.9 1151.38
  5242.0 1151.51  5249.1 1153.14  5256.1 1153.40  5270.3 1155.69  5290.8 1156.69
#Mann=5,-1,0
  4704.8    0.12       0  4947.0    0.05       0  5001.0    0.03       0
  5005.0    0.05       0  5099.9    0.12       0
Bank Sta=5001,5005
Exp/Cntr=0.3,0.1

Type RM Length L Ch R = 1,3587,445,445,445
BEGIN DESCRIPTION:
Mapping XS 2e103a16
END DESCRIPTION:
XS GIS Cut Line= 2
      2798193.61     10223609.73      2798712.55     10223644.33
#Sta/Elev= 30
  4557.5 1154.06  4564.2 1154.01  4589.6 1152.88  4639.8 1151.67  4673.5 1149.77
  4679.2 1149.35  4709.9 1148.44  4730.0 1146.58  4750.0 1145.92  4760.0 1146.97
  4790.1 1147.91  4820.2 1148.68  4837.9 1148.58  4860.2 1148.82  4890.3 1148.10
  4930.4 1148.38  4940.7 1148.72  4960.5 1145.25  4970.5 1144.70  4979.8 1143.64
  4982.8 1142.65  4983.1 1142.15  4986.6 1142.15  4986.8 1142.65  4990.5 1143.67
  5000.6 1144.34  5010.6 1145.89  5020.6 1146.85  5050.7 1148.03  5077.6 1147.30
#Mann=7,-1,0
  4557.5    0.05       0  4564.2    0.12       0  4673.5    0.05       0
  4837.9    0.12       0  4940.7    0.05       0  4982.8    0.05       0
  4986.8    0.05       0
Bank Sta=4982.8,4986.8
Exp/Cntr=0.3,0.1

Type RM Length L Ch R = 1,3142,642,642,642
BEGIN DESCRIPTION:
Mapping XS db8e9d5c
END DESCRIPTION:
XS GIS Cut Line= 2
      2798150.27     10223956.96      2798566.95     10223983.00
#Sta/Elev= 30
  4670.8 1148.29  4688.2 1147.55  4696.3 1147.42  4706.3 1146.75  4726.3 1146.49
  4786.9 1144.50  4816.5 1143.61  4836.5 1143.45  4845.6 1143.05  4886.6 1142.43
  4896.7 1140.87  4916.7 1139.82  4926.7 1141.67  4936.7 1142.41  4946.8 1142.32
  4966.8 1141.08  4976.8 1141.27  4986.8 1139.81  4994.9 1139.01  4995.1 1138.51
  4998.6 1138.51  4998.9 1139.01  5005.9 1139.75  5010.9 1139.39  5016.9 1139.53
  5036.9 1143.94  5046.9 1144.25  5057.0 1143.37  5077.0 1143.67  5088.3 1143.38
#Mann=5,-1,0
  4670.8    0.05       0  4688.2    0.12       0  4786.9    0.05       0
  4994.9    0.03       0  4998.9    0.05       0
Bank Sta=4994.9,4998.9
Exp/Cntr=0.3,0.1

Type RM Length L Ch R = 1,2500,500,500,500
BEGIN DESCRIPTION:
SANFERNANDO026 5.0
END DESCRIPTION:
XS GIS Cut Line= 3
      2798355.71     10224503.10      2798578.65     10224395.16
      2799505.72     10223703.08
#Sta/Elev= 30
  4752.3 1142.71  4806.0 1143.18  4818.9 1141.96  4873.7 1140.46  4941.1 1137.19
  4952.6 1135.90  4960.4 1136.35  4969.6 1136.48  5019.3 1132.86  5019.5 1132.36
  5023.3 1132.86  5028.0 1135.30  5036.3 1136.86  5048.8 1138.23  5071.1 1138.58
  5184.3 1140.37  5192.7 1139.76  5284.4 1141.17  5378.2 1141.09  5449.1 1142.69
  5534.6 1146.01  5563.8 1146.19  5620.3 1148.67  5699.3 1150.52  5807.4 1155.66
  5968.1 1161.62  5973.8 1161.78  6043.3 1165.44  6143.3 1173.37  6156.9 1173.70
#Mann=8,-1,0
  4752.3    0.12       0  4960.4    0.05       0  5019.3    0.03       0
  5023.3    0.05       0  5036.3    0.12       0  5071.1    0.05       0
  5968.1    0.12       0  5973.8    0.05       0
Bank Sta=5019.3,5023.3
Exp/Cntr=0.3,0.1

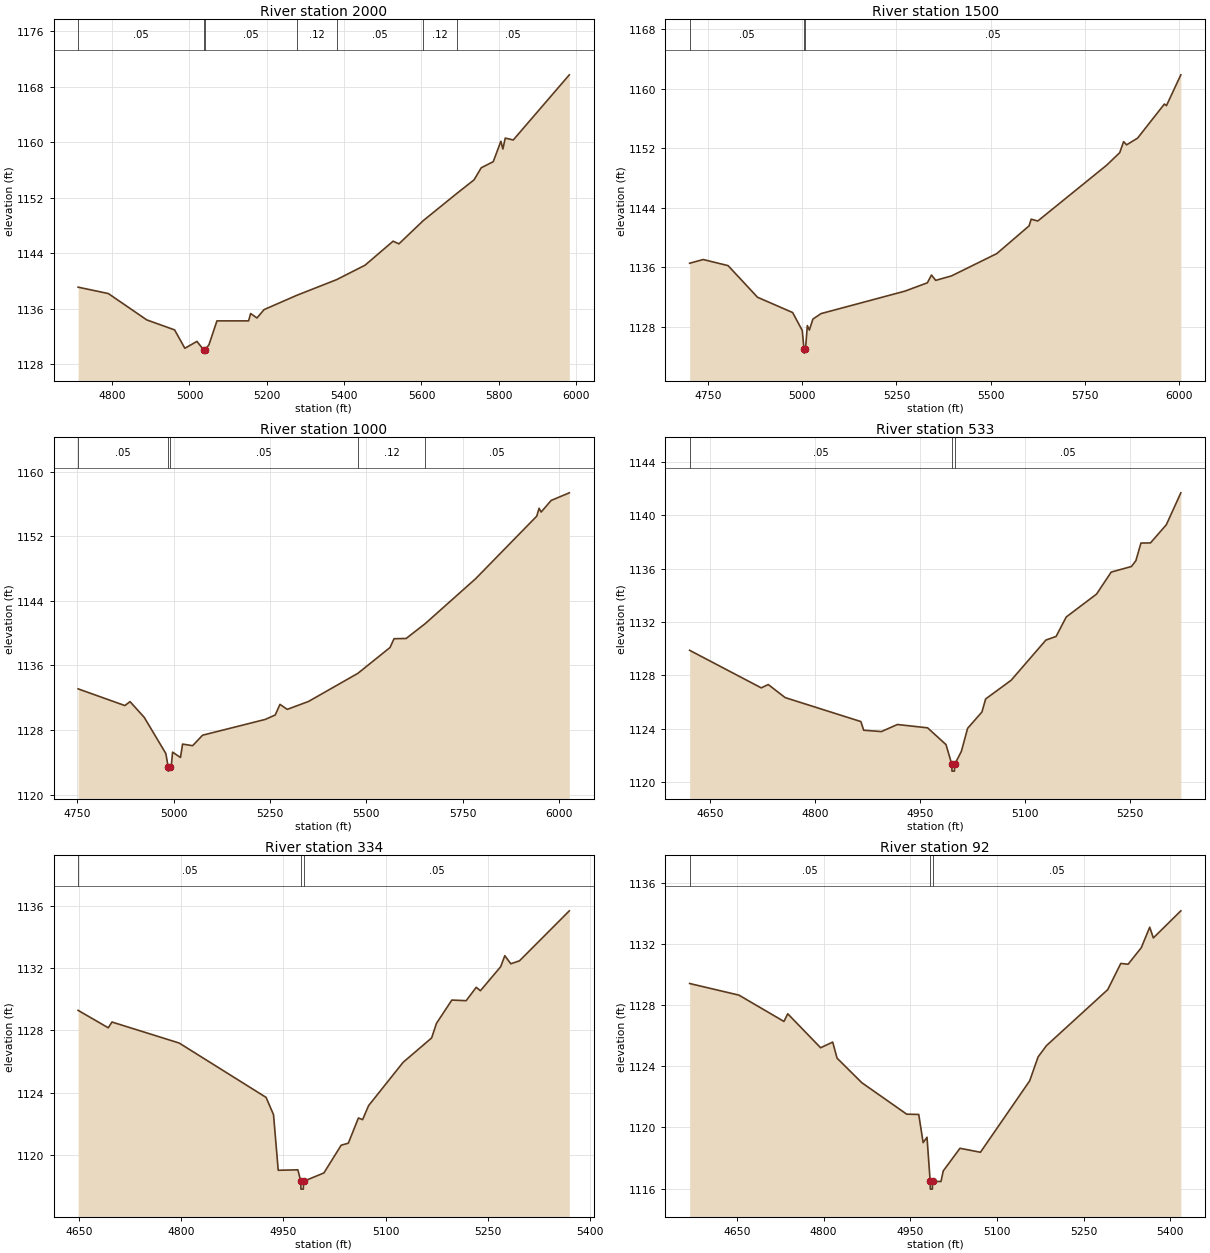
Type RM Length L Ch R = 1,2000,500,500,500
BEGIN DESCRIPTION:
SANFERNANDO026 4.0
END DESCRIPTION:
XS GIS Cut Line= 3
      2798480.67     10224678.11      2798757.17     10224759.04
      2799705.65     10224503.12
#Sta/Elev= 30
  4711.9 1139.08  4790.1 1138.16  4889.5 1134.36  4961.5 1132.92  4988.0 1130.27
  5019.2 1131.26  5036.3 1130.07  5036.6 1129.57  5040.3 1130.07  5050.3 1130.77
  5071.0 1134.22  5152.9 1134.22  5158.1 1135.28  5174.5 1134.64  5192.8 1135.84
  5277.3 1137.90  5380.8 1140.17  5454.2 1142.25  5526.7 1145.71  5541.6 1145.32
  5604.6 1148.67  5691.2 1152.58  5736.0 1154.55  5754.6 1156.29  5785.6 1157.17
  5805.4 1160.11  5810.6 1159.00  5816.7 1160.57  5837.4 1160.30  5982.4 1169.69
#Mann=7,-1,0
  4711.9    0.05       0  5036.3    0.03       0  5040.3    0.05       0
  5277.3    0.12       0  5380.8    0.05       0  5604.6    0.12       0
  5691.2    0.05       0
Bank Sta=5036.3,5040.3
Exp/Cntr=0.3,0.1

Type RM Length L Ch R = 1,1500,500,500,500
BEGIN DESCRIPTION:
SANFERNANDO026 3.0
END DESCRIPTION:
XS GIS Cut Line= 3
      2798430.71     10225028.13      2798679.69     10225193.88
      2799605.71     10224803.10
#Sta/Elev= 30
  4700.9 1136.55  4736.9 1137.05  4803.0 1136.23  4881.2 1131.98  4974.4 1129.93
  5000.0 1127.52  5004.5 1124.98  5004.8 1124.48  5008.5 1124.98  5013.4 1128.18
  5018.8 1127.58  5028.2 1129.05  5049.9 1129.79  5272.2 1132.80  5332.1 1133.92
  5343.0 1134.97  5354.2 1134.25  5396.2 1134.85  5516.6 1137.85  5602.2 1141.57
  5607.7 1142.47  5625.2 1142.22  5808.2 1149.72  5842.8 1151.40  5853.1 1152.88
  5861.1 1152.45  5890.2 1153.35  5961.4 1157.93  5966.8 1157.71  6005.1 1161.85
#Mann=3,-1,0
  4700.9    0.05       0  5004.5    0.03       0  5008.5    0.05       0
Bank Sta=5004.5,5008.5
Exp/Cntr=0.3,0.1

Type RM Length L Ch R = 1,1000,467,467,467
BEGIN DESCRIPTION:
SANFERNANDO026 2.0
END DESCRIPTION:
XS GIS Cut Line= 3
      2798380.68     10225328.11      2798534.50     10225522.00
      2799505.71     10225853.12
#Sta/Elev= 30
  4752.5 1133.10  4873.8 1131.03  4887.1 1131.52  4924.0 1129.57  4980.0 1125.09
  4986.1 1123.41  4986.3 1122.91  4990.1 1123.41  4994.4 1123.75  4997.5 1125.26
  5018.0 1124.60  5023.3 1126.26  5049.4 1126.06  5075.2 1127.36  5237.4 1129.31
  5263.5 1129.86  5275.9 1131.18  5294.8 1130.56  5349.9 1131.54  5477.8 1135.02
  5561.2 1138.22  5571.6 1139.31  5603.0 1139.34  5652.0 1141.16  5783.1 1146.74
  5941.6 1154.49  5947.7 1155.47  5953.0 1155.00  5979.1 1156.44  6026.1 1157.38
#Mann=5,-1,0
  4752.5    0.05       0  4986.1    0.05       0  4990.1    0.05       0
  5477.8    0.12       0  5652.0    0.05       0
Bank Sta=4986.1,4990.1
Exp/Cntr=0.3,0.1

Type RM Length L Ch R = 1,533,199,199,199
BEGIN DESCRIPTION:
Mapping XS 5c0e1074
END DESCRIPTION:
XS GIS Cut Line= 4
      2798365.79     10225451.49      2798338.90     10225690.82
      2798379.24     10225868.33      2798550.74     10226088.06
#Sta/Elev= 30
  4620.8 1129.88  4723.1 1127.06  4733.1 1127.31  4757.2 1126.33  4865.4 1124.53
  4869.4 1123.88  4894.7 1123.78  4917.6 1124.31  4960.7 1124.06  4987.0 1122.80
  4995.3 1121.31  4995.5 1120.81  4999.0 1120.81  4999.3 1121.31  5008.9 1122.29
  5017.8 1124.02  5038.3 1125.25  5043.6 1126.23  5080.0 1127.63  5129.7 1130.65
  5144.2 1130.92  5158.7 1132.38  5202.0 1134.10  5222.9 1135.75  5251.8 1136.17
  5258.2 1136.61  5265.4 1137.93  5279.0 1137.94  5301.6 1139.30  5322.4 1141.70
#Mann=3,-1,0
  4620.8    0.05       0  4995.3    0.03       0  4999.3    0.05       0
Bank Sta=4995.3,4999.3
Exp/Cntr=0.3,0.1

Type RM Length L Ch R = 1,334,242,242,242
BEGIN DESCRIPTION:
Mapping XS 5f1af373
END DESCRIPTION:
XS GIS Cut Line= 4
      2798320.06     10225481.05      2798185.59     10225784.95
      2798185.59     10225838.74      2798376.57     10226113.11
#Sta/Elev= 30
  4648.9 1129.29  4693.1 1128.17  4698.6 1128.54  4797.2 1127.19  4924.6 1123.70
  4935.5 1122.59  4942.4 1119.02  4971.2 1119.05  4975.5 1118.31  4975.7 1117.81
  4979.2 1117.81  4979.5 1118.31  5009.4 1118.85  5034.7 1120.63  5045.2 1120.76
  5060.0 1122.38  5066.1 1122.27  5074.9 1123.17  5125.5 1125.95  5167.4 1127.52
  5174.4 1128.45  5197.0 1129.95  5218.0 1129.91  5232.8 1130.77  5238.9 1130.55
  5268.6 1132.09  5274.7 1132.80  5283.5 1132.28  5296.2 1132.47  5369.3 1135.68
#Mann=3,-1,0
  4648.9    0.05       0  4975.5    0.03       0  4979.5    0.05       0
Bank Sta=4975.5,4979.5
Exp/Cntr=0.3,0.1

Type RM Length L Ch R = 1,92,0,0,0
BEGIN DESCRIPTION:
SANFERNANDO026 1.0
END DESCRIPTION:
XS GIS Cut Line= 3
      2798230.70     10225478.09      2797946.00     10225803.00
      2798199.70     10226135.83
#Sta/Elev= 30
  4568.0 1129.41  4653.4 1128.65  4731.3 1126.93  4737.9 1127.43  4794.8 1125.21
  4815.7 1125.58  4823.3 1124.53  4866.0 1122.93  4943.8 1120.87  4964.7 1120.85
  4972.3 1119.01  4979.0 1119.36  4984.5 1116.47  4984.8 1115.97  4988.3 1115.97
  4988.5 1116.47  5003.2 1116.47  5007.1 1117.16  5036.1 1118.64  5071.5 1118.38
  5156.8 1123.05  5171.3 1124.61  5185.8 1125.35  5291.9 1129.01  5314.5 1130.72
  5327.2 1130.67  5350.0 1131.75  5364.6 1133.09  5370.9 1132.39  5418.5 1134.16
#Mann=3,-1,0
  4568.0    0.05       0  4984.5    0.03       0  4988.5    0.05       0
Bank Sta=4984.5,4988.5
Exp/Cntr=0.3,0.1

Chan Stop Cuts=-1