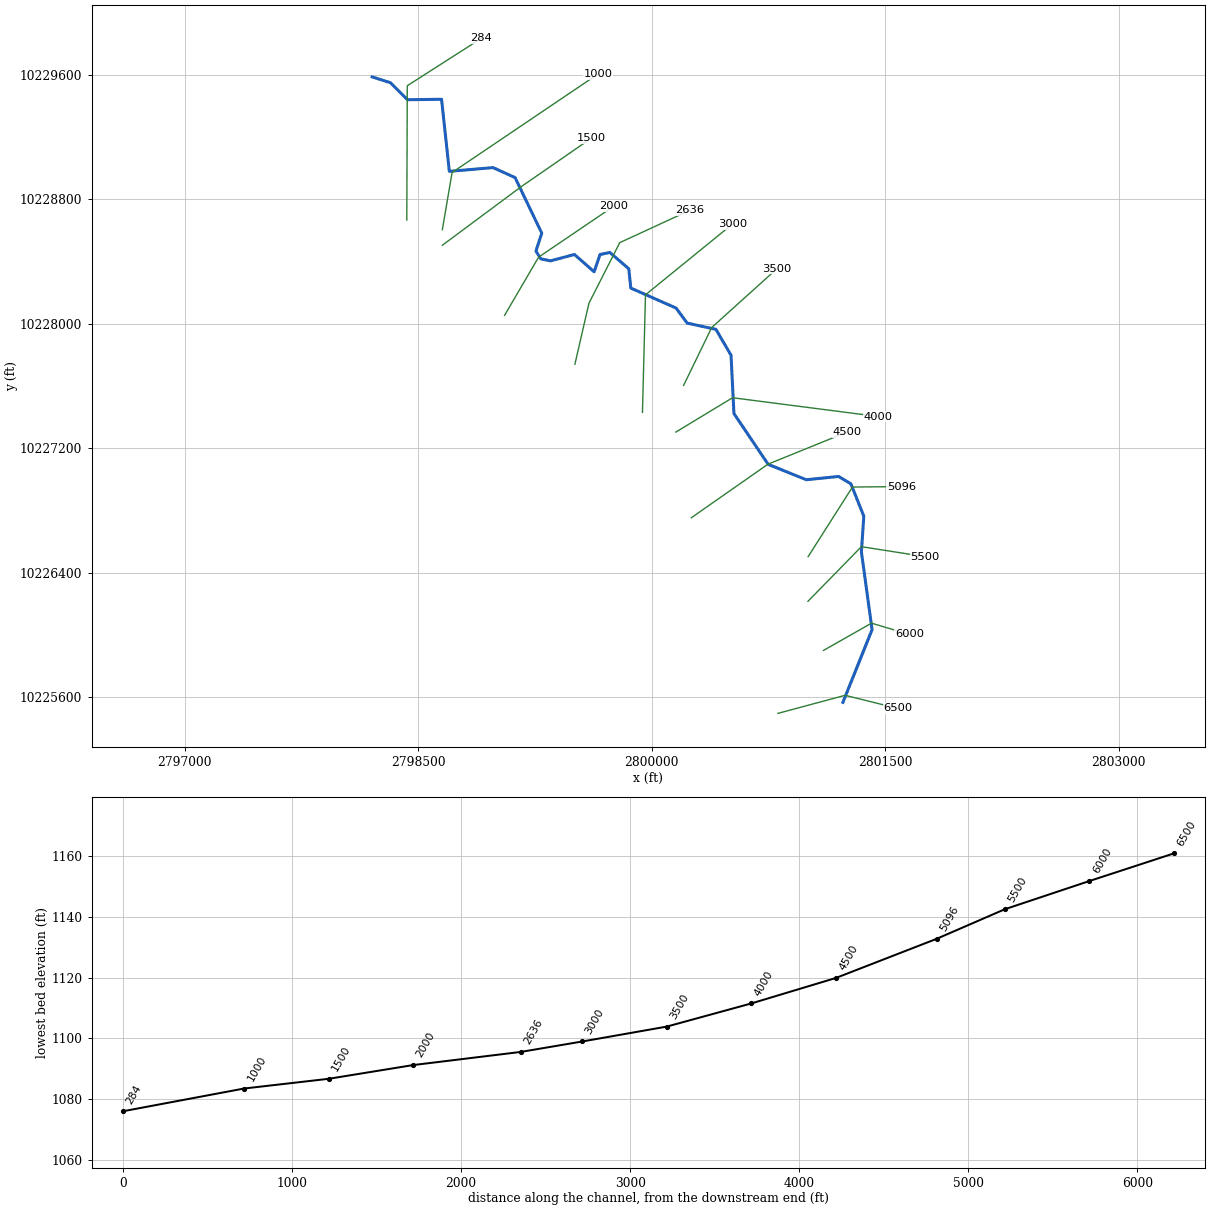
--- SANFERNANDO028.prj (project) ---

Proj Title=SANFERNANDO028 Base Level Engineering
Current Plan=p01
Default Exp/Contr=0.3,0.1
English Units
Geom File=g01
Flow File=f01
Plan File=p01
Y Axis Title=Elevation
X Axis Title(PF)=Main Channel Distance
X Axis Title(XS)=Station
BEGIN DESCRIPTION:
SANFERNANDO028
END DESCRIPTION:
DSS Export Rating Curves= 0
DSS Export Rating Curve Sorted= 0
DSS Export Volume Flow Curves= 0
DXF OffsetX= 0
DXF OffsetY= 0
DXF ScaleX= 1
DXF ScaleY= 10

--- SANFERNANDO028.p01 (plan) ---

Plan Title=Multiple Run
Short Identifier=Multiple
Geom File=g01
Flow File=f01
Subcritical Flow
K Sum by GR= 0
Std Step Tol= 0.01
Critical Tol= 0.01
Num of Std Step Trials= 20
Max Error Tol= 0.3
Flow Tol Ratio= 0.001
Split Flow NTrial= 30
Split Flow Tol= 0.02
Split Flow Ratio= 0.02
Log Output Level= 0
Friction Slope Method= 1
Unsteady Friction Slope Method= 2
Unsteady Bridges Friction Slope Method= 1
Parabolic Critical Depth
Global Vel Dist=  1 , 1 , 1
Global Log Level= 0
CheckData=True
Encroach Param= -1, 0, 0, 0
BEGIN DESCRIPTION:
Multiple Run
END DESCRIPTION:

--- SANFERNANDO028.f01 (steady flow) ---

Flow Title=Multiple
Number of Profiles=7
Profile Names=10-year,25-year,50-year,1pct_min,100-year,1pct_plu,500-year
River Rch & RM= SANFERNANDO028,Reach-1,6500
     247     387     476     305     621    1262     858
Boundary for River Rch & Prof#=SANFERNANDO028,Reach-1,1
Up Type=0
Dn Type=3
Dn Slope=0.005
Boundary for River Rch & Prof#=SANFERNANDO028,Reach-1,2
Up Type=0
Dn Type=3
Dn Slope=0.005
Boundary for River Rch & Prof#=SANFERNANDO028,Reach-1,3
Up Type=0
Dn Type=3
Dn Slope=0.005
Boundary for River Rch & Prof#=SANFERNANDO028,Reach-1,4
Up Type=0
Dn Type=3
Dn Slope=0.005
Boundary for River Rch & Prof#=SANFERNANDO028,Reach-1,5
Up Type=0
Dn Type=3
Dn Slope=0.005
Boundary for River Rch & Prof#=SANFERNANDO028,Reach-1,6
Up Type=0
Dn Type=3
Dn Slope=0.005
Boundary for River Rch & Prof#=SANFERNANDO028,Reach-1,7
Up Type=0
Dn Type=3
Dn Slope=0.005

--- SANFERNANDO028.g01 (geometry) ---

Geom Title=Existing Conditions
Program Version=4.10

River Reach=SANFERNANDO028  ,Reach-1
Reach XY= 30
        2801229.       10225567.      2801416.25       10226034.
      2801347.75       10226534.      2801363.25       10226763.
        2801280.       10226971.      2801201.75       10227018.
       2800993.5       10226997.      2800748.75       10227096.
        2800529.       10227422.      2800510.25       10227797.
      2800413.25       10227963.        2800229.       10228003.
        2800157.       10228100.       2799866.5       10228228.
       2799853.5       10228352.        2799732.       10228457.
        2799669.       10228444.      2799630.75       10228333.
        2799504.       10228444.      2799350.75       10228403.
      2799288.25       10228416.        2799257.       10228466.
       2799294.5       10228581.        2799123.       10228938.
       2798981.5       10229002.      2798700.75       10228978.
      2798650.75       10229441.        2798432.       10229438.
      2798323.25       10229547.      2798204.25       10229585.

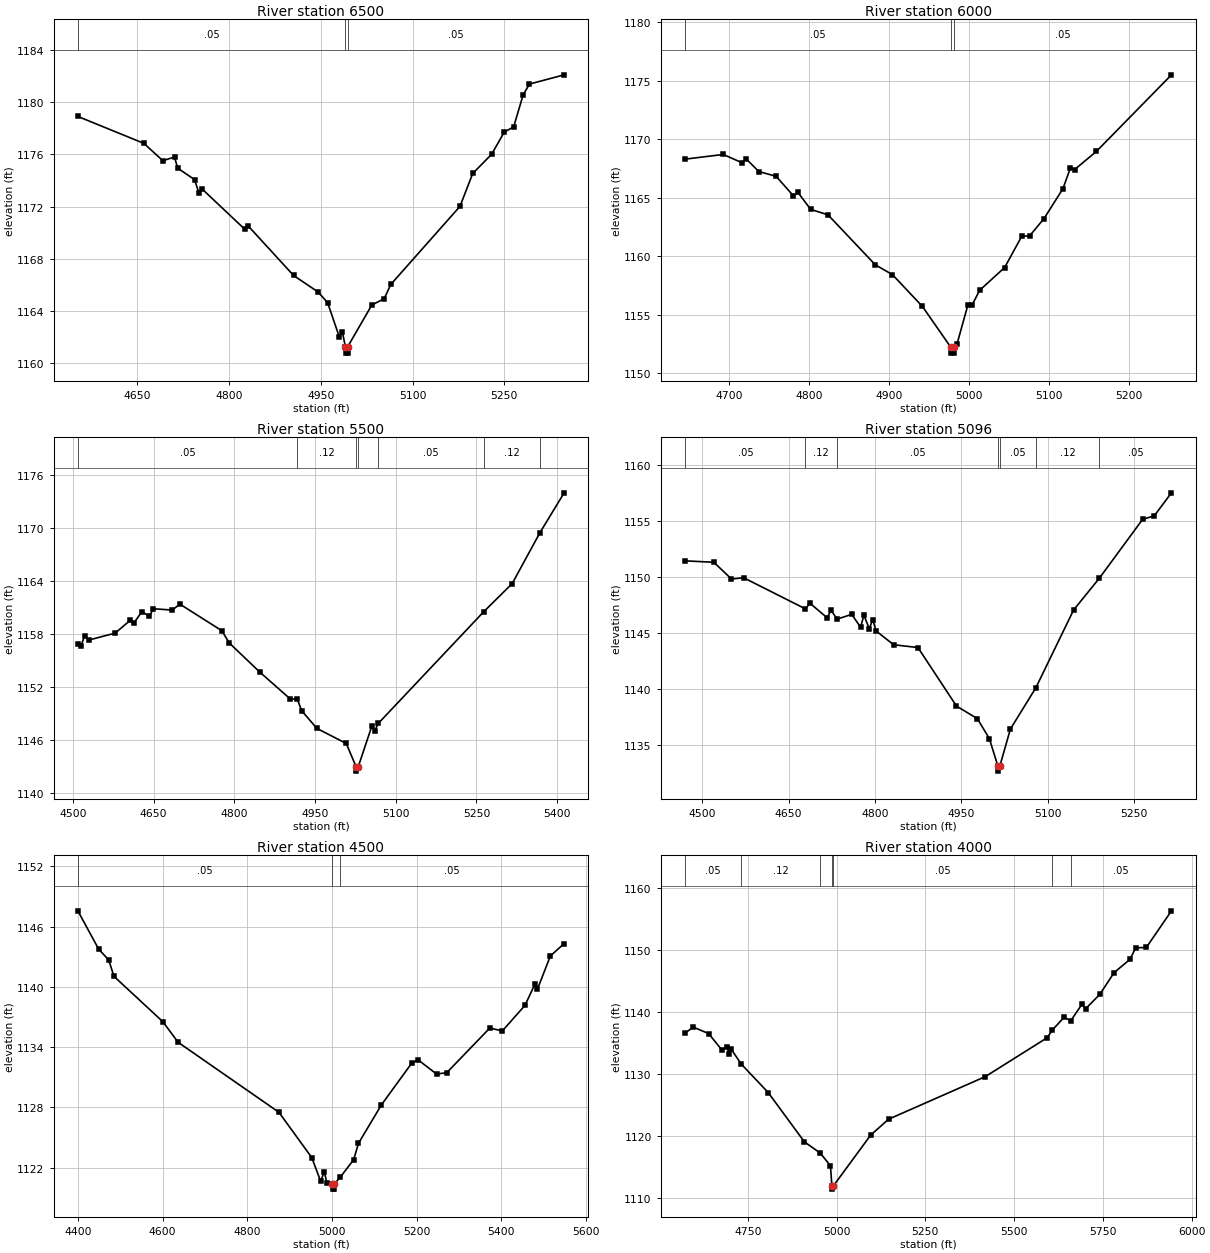
Type RM Length L Ch R = 1 ,6500    ,500,500,500
BEGIN DESCRIPTION:
SANFERNANDO028 13.0
END DESCRIPTION:
XS GIS Cut Line= 3
      2800811.54     10225496.17       2801243.2     10225612.27
      2801580.66     10225528.12
#Sta/Elev= 30
    4553 1178.91  4660.8 1176.85  4691.9 1175.52    4711  1175.8  4716.1 1174.95
  4743.7 1174.07  4750.9 1173.04  4756.1 1173.35  4825.7 1170.27  4830.8 1170.55
  4905.6 1166.72  4945.6 1165.46  4961.2 1164.64  4980.3 1162.02  4985.5 1162.36
  4990.2 1161.27  4990.5 1160.77    4994 1160.77  4994.2 1161.27  5033.5 1164.46
  5053.7 1164.94  5064.4 1166.03  5177.6 1172.02  5198.4 1174.54  5229.3 1176.01
  5249.9 1177.71  5265.3 1178.11  5280.8 1180.56  5291.1 1181.39  5347.8  1182.1
#Mann= 3 ,-1 , 0
    4553     .05       0  4990.2     .03       0  4994.2     .05       0
Bank Sta=4990.2,4994.2
XS Rating Curve= 0 ,0
Exp/Cntr=0.3,0.1

Type RM Length L Ch R = 1 ,6000    ,500,500,500
BEGIN DESCRIPTION:
SANFERNANDO028 12.0
END DESCRIPTION:
XS GIS Cut Line= 3
      2801104.35     10225900.42      2801412.68     10226075.76
      2801655.65     10226003.12
#Sta/Elev= 30
  4645.3 1168.29  4692.9 1168.69  4715.8    1168  4721.6 1168.31  4737.4 1167.23
  4759.1 1166.82  4780.7 1165.15  4786.4 1165.44  4802.3 1163.99  4823.9 1163.53
    4883 1159.26  4904.6 1158.41  4942.1 1155.69  4977.6  1152.2  4977.9  1151.7
  4981.4  1151.7  4981.6  1152.2  4985.4 1152.49  4998.9 1155.81  5004.2 1155.81
  5013.6 1157.07  5044.9 1159.02  5066.3 1161.69  5076.2 1161.73  5094.2 1163.21
  5117.9 1165.77  5127.3 1167.56  5132.5  1167.4  5159.7 1168.95  5253.6  1175.5
#Mann= 3 ,-1 , 0
  4645.3     .05       0  4977.6     .05       0  4981.6     .05       0
Bank Sta=4977.6,4981.6
XS Rating Curve= 0 ,0
Exp/Cntr=0.3,0.1

Type RM Length L Ch R = 1 ,5500    ,404,404,404
BEGIN DESCRIPTION:
SANFERNANDO028 11.0
END DESCRIPTION:
XS GIS Cut Line= 3
       2801004.5     10226216.19      2801347.75     10226566.99
      2801755.68     10226503.11
#Sta/Elev= 30
  4509.2 1156.81    4515 1156.61    4522 1157.79  4529.1 1157.27  4578.5 1158.06
  4606.8 1159.52    4614 1159.26  4628.1 1160.48  4642.3 1159.96  4649.3 1160.82
  4684.7 1160.67  4698.8 1161.34  4776.6 1158.34  4790.7 1156.94  4847.3 1153.65
  4903.9 1150.61  4917.2 1150.57    4925 1149.29  4953.3 1147.28    5008 1145.57
  5026.3 1142.94  5026.5 1142.44  5030.3 1142.94  5055.5 1147.53  5060.6 1146.95
  5067.5 1147.84  5263.3 1160.47  5316.4 1163.67  5367.6 1169.39  5412.9 1173.94
#Mann= 7 ,-1 , 0
  4509.2     .05       0  4917.2     .12       0  5026.3     .07       0
  5030.3     .12       0  5067.5     .05       0  5263.3     .12       0
  5367.6     .05       0
Bank Sta=5026.3,5030.3
XS Rating Curve= 0 ,0
Exp/Cntr=0.3,0.1

Type RM Length L Ch R = 1 ,5096    ,596,596,596
BEGIN DESCRIPTION:
SANFERNANDO028 10.0
END DESCRIPTION:
XS GIS Cut Line= 3
      2801005.68     10226503.11      2801290.25       10226950.
      2801605.63     10226953.11
#Sta/Elev= 30
  4470.2 1151.48  4520.1 1151.35  4550.6 1149.86  4571.8 1149.97  4679.3 1147.19
  4686.9  1147.7  4717.4 1146.38  4723.3  1147.1  4734.3 1146.28  4759.7  1146.7
    4775 1145.56  4780.9 1146.62  4790.2 1145.42  4796.1 1146.24  4802.1 1145.22
  4832.5 1143.99  4874.8 1143.74  4941.7 1138.52  4978.1 1137.39  4998.9 1135.61
  5013.4 1133.21  5013.7 1132.71  5017.4 1133.21  5035.4 1136.46  5079.7 1140.15
  5145.4  1147.1  5189.8 1149.91  5265.4 1155.19  5285.4 1155.49  5315.4 1157.55
#Mann= 7 ,-1 , 0
  4470.2     .05       0  4679.3     .12       0  4734.3     .05       0
  5013.4     .05       0  5017.4     .05       0  5079.7     .12       0
  5189.8     .05       0
Bank Sta=5013.4,5017.4
XS Rating Curve= 0 ,0
Exp/Cntr=0.3,0.1

Type RM Length L Ch R = 1 ,4500    ,500,500,500
BEGIN DESCRIPTION:
SANFERNANDO028 9.0
END DESCRIPTION:
XS GIS Cut Line= 3
       2800255.7     10226753.13      2800747.75       10227097.
      2801255.72     10227303.13
#Sta/Elev= 30
  4399.7 1147.57  4448.9 1143.75  4472.5 1142.68  4485.1 1141.04  4600.7 1136.52
  4636.5 1134.48  4874.6 1127.51  4952.2    1123  4973.1 1120.65  4981.8 1121.59
  4987.9 1120.47  5001.1 1120.36  5001.3 1119.86  5004.8 1119.86  5005.1 1120.36
  5019.4 1121.04  5051.2  1122.8  5062.5 1124.42  5116.5 1128.24  5187.9 1132.38
  5202.8 1132.75  5246.8 1131.32  5270.9 1131.45  5372.7  1135.9  5402.2 1135.61
  5455.8 1138.16  5479.8 1140.33  5485.2 1139.77  5515.8 1143.08  5548.2 1144.31
#Mann= 3 ,-1 , 0
  4399.7     .05       0  5001.1     .05       0  5019.4     .05       0
Bank Sta=5001.1,5005.1
XS Rating Curve= 0 ,0
Exp/Cntr=0.3,0.1

Type RM Length L Ch R = 1 ,4000    ,500,500,500
BEGIN DESCRIPTION:
SANFERNANDO028 8.0
END DESCRIPTION:
XS GIS Cut Line= 3
      2800155.71     10227303.13      2800520.32     10227523.83
      2801455.66     10227403.11
#Sta/Elev= 30
  4573.8 1136.63    4597 1137.56  4639.7 1136.53  4676.6 1133.93  4690.7 1134.32
  4697.9 1133.27  4703.7    1134  4731.4 1131.64  4807.6 1127.04  4909.3 1119.12
  4954.3 1117.29  4982.9 1115.26  4986.9    1112  4987.1  1111.5  4990.9    1112
  5096.2  1120.2  5146.6 1122.75  5418.8  1129.6  5593.4 1135.87  5607.2 1137.07
  5640.6 1139.14  5659.7  1138.6    5691 1141.24  5701.1  1140.5  5741.5 1142.85
  5781.8 1146.35  5826.5 1148.48  5842.3 1150.32  5872.5 1150.39  5943.1 1156.28
#Mann= 7 ,-1 , 0
  4573.8     .05       0  4731.4     .12       0  4954.3     .05       0
  4986.9     .05       0  4990.9     .05       0  5607.2     .12       0
  5659.7     .05       0
Bank Sta=4986.9,4990.9
XS Rating Curve= 0 ,0
Exp/Cntr=0.3,0.1

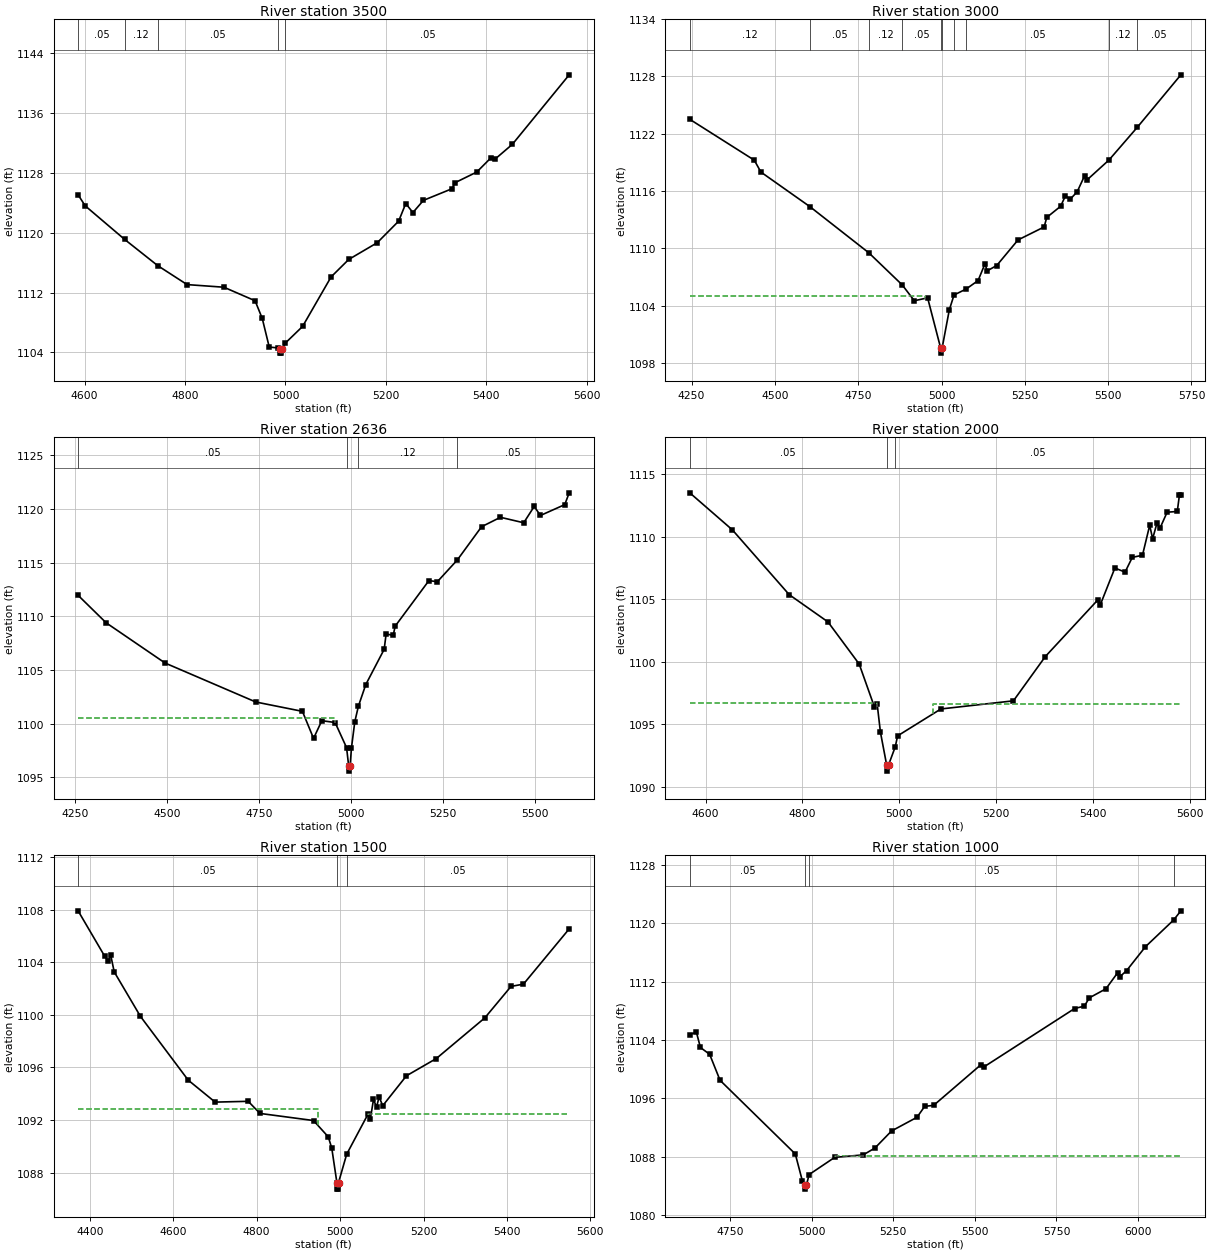
Type RM Length L Ch R = 1 ,3500    ,500,500,500
BEGIN DESCRIPTION:
SANFERNANDO028 7.0
END DESCRIPTION:
XS GIS Cut Line= 3
      2800205.69     10227603.12      2800386.03     10227974.67
      2800805.69     10228353.12
#Sta/Elev= 30
    4587 1125.07  4601.1 1123.59  4679.7  1119.1  4745.5  1115.6  4804.1 1113.06
  4877.4 1112.71  4939.5  1110.9  4953.8 1108.53  4967.7 1104.71  4984.7  1104.6
  4988.2  1104.4  4988.5  1103.9    4992  1103.9  4992.2  1104.4    5000 1105.26
  5034.1 1107.47  5090.9 1114.09    5126 1116.42  5182.8 1118.66  5225.4 1121.54
  5239.6  1123.9  5253.8 1122.69  5274.8 1124.32  5331.5 1125.87  5338.3  1126.7
  5380.9  1128.1  5409.3 1130.01  5416.7 1129.79  5451.9 1131.81  5565.1  1141.1
#Mann= 5 ,-1 , 0
    4587     .05       0  4679.7     .12       0  4745.5     .05       0
  4984.7     .05       0    5000     .05       0
Bank Sta=4988.2,4992.2
XS Rating Curve= 0 ,0
Exp/Cntr=0.3,0.1

Type RM Length L Ch R = 1 ,3000    ,364,364,364
BEGIN DESCRIPTION:
SANFERNANDO028 6.0
END DESCRIPTION:
XS GIS Cut Line= 3
      2799941.33     10227429.66       2799960.7     10228184.81
      2800517.73     10228638.01
#Sta/Elev= 30
  4244.6 1123.51  4438.1 1119.23  4458.1 1117.98    4605 1114.36  4781.9 1109.52
  4882.3 1106.15  4918.3  1104.5  4958.3  1104.8  4997.6 1099.51  4997.9 1099.01
  5001.6 1099.51  5023.4 1103.55  5037.5  1105.1    5074 1105.73  5109.6 1106.61
  5130.4 1108.37  5136.9 1107.63  5165.6 1108.19  5229.5 1110.87  5307.8 1112.23
  5315.8 1113.23  5357.4  1114.4  5371.7 1115.49  5386.1 1115.14  5406.9 1115.91
  5429.2 1117.59  5435.7 1117.13  5502.6 1119.25  5587.1 1122.66  5718.1 1128.17
#Mann= 10 ,-1 , 0
  4244.6     .12       0    4605     .05       0  4781.9     .12       0
  4882.3     .05       0  4997.6     .05       0  5001.6     .05       0
  5037.5     .12       0    5074     .05       0  5502.6     .12       0
  5587.1     .05       0
#XS Ineff= 2 , 0
         4949.09    1105
Permanent Ineff=
       F       F
Bank Sta=4997.6,5001.6
XS Rating Curve= 0 ,0
Exp/Cntr=0.3,0.1

Type RM Length L Ch R = 1 ,2636    ,636,636,636
BEGIN DESCRIPTION:
Mapping XS 82c0d65d
END DESCRIPTION:
XS GIS Cut Line= 4
      2799507.31     10227738.72      2799597.58     10228131.05
       2799795.5     10228519.94      2800246.71      10228728.2
#Sta/Elev= 30
  4257.1 1111.96  4333.4  1109.4  4493.8 1105.65  4740.5 1102.02  4867.3 1101.15
  4897.6 1098.63  4920.1 1100.28  4956.2 1100.11  4987.4 1097.77  4993.1 1096.08
  4993.4 1095.58  4997.1 1096.08  5000.7 1097.75  5009.8 1100.18  5019.5 1101.62
  5039.6 1103.64  5089.7 1106.93    5095 1108.36  5114.2 1108.23  5119.7 1109.09
  5211.4 1113.33  5234.4 1113.23  5288.8 1115.26  5354.6 1118.35    5406 1119.23
  5469.3 1118.72  5497.8 1120.24  5514.8  1119.4  5580.9 1120.41    5593 1121.51
#Mann= 4 ,-1 , 0
  4257.1     .05       0  4987.4     .05       0  5019.5     .12       0
  5288.8     .05       0
#XS Ineff= 2 , 0
         4956.48  1100.5
Permanent Ineff=
       F       F
Bank Sta=4993.1,4997.1
XS Rating Curve= 0 ,0
Exp/Cntr=0.3,0.1

Type RM Length L Ch R = 1 ,2000    ,500,500,500
BEGIN DESCRIPTION:
SANFERNANDO028 4.0
END DESCRIPTION:
XS GIS Cut Line= 3
      2799055.68     10228053.11      2799274.13     10228426.73
      2799755.65     10228753.09
#Sta/Elev= 30
  4567.2 1113.52  4655.2 1110.56  4772.6 1105.38  4852.7  1103.2  4917.2 1099.83
  4948.6 1096.41  4954.4 1096.61  4961.1 1094.38  4973.9 1091.77  4974.1 1091.27
  4977.9 1091.77  4991.6  1093.2  4996.6 1094.09    5086 1096.24  5235.8 1096.89
  5301.7 1100.43  5409.5 1104.93  5415.5 1104.59  5445.4 1107.51  5466.4 1107.18
  5481.4 1108.36  5502.4 1108.53  5517.3 1110.92  5523.4 1109.85  5532.3 1111.09
  5538.3 1110.67  5553.3 1111.97  5574.3 1112.03  5578.7 1113.33  5581.7 1113.33
#Mann= 3 ,-1 , 0
  4567.2     .05       0  4973.9     .05       0  4991.6     .05       0
#XS Ineff= 2 , 0
            4955  1096.7 5068.86         1096.64
Permanent Ineff=
       F       F
Bank Sta=4973.9,4977.9
XS Rating Curve= 0 ,0
Exp/Cntr=0.3,0.1

Type RM Length L Ch R = 1 ,1500    ,500,500,500
BEGIN DESCRIPTION:
SANFERNANDO028 3.0
END DESCRIPTION:
XS GIS Cut Line= 3
      2798655.69     10228503.12      2799159.77     10228877.67
      2799611.46     10229190.07
#Sta/Elev= 30
    4372  1107.9  4435.6 1104.46    4444  1104.1  4450.2 1104.53  4458.6 1103.26
  4521.5 1099.88  4635.9 1095.04  4700.5 1093.37  4779.8 1093.43    4808 1092.51
  4936.3 1091.97  4971.7 1090.73  4980.1 1089.87  4992.3 1087.26  4992.6 1086.76
  4996.1 1086.76  4996.3 1087.26  5015.8 1089.41  5066.5 1092.43  5072.6  1092.1
  5080.1 1093.57  5087.4 1092.99  5093.5 1093.76  5102.3  1093.1  5159.1 1095.37
  5230.7 1096.68    5347 1099.77  5409.8 1102.16  5439.5 1102.33  5549.2 1106.53
#Mann= 3 ,-1 , 0
    4372     .05       0  4992.3     .05       0  5015.8     .05       0
#XS Ineff= 2 , 0
         4947.73 1092.86 5067.05          1092.5
Permanent Ineff=
       F       F
Bank Sta=4992.3,4996.3
XS Rating Curve= 0 ,0
Exp/Cntr=0.3,0.1

Type RM Length L Ch R = 1 ,1000    ,716,716,716
BEGIN DESCRIPTION:
SANFERNANDO028 2.0
END DESCRIPTION:
XS GIS Cut Line= 3
      2798655.68     10228603.11      2798718.42     10228970.49
       2799655.7     10229603.12
#Sta/Elev= 30
  4627.3 1104.75  4647.6 1105.09  4659.9 1102.99  4688.2 1102.05    4720 1098.49
  4950.4 1088.39  4972.2 1084.67  4980.4 1084.07  4980.6 1083.57  4984.4 1084.07
  4992.5 1085.56  5071.2 1087.93  5158.1 1088.26  5194.1  1089.2    5245 1091.54
    5323 1093.42  5346.6 1094.92  5373.9 1095.05  5517.8 1100.59  5526.7 1100.29
  5805.6 1108.33  5835.5 1108.66  5850.5 1109.79  5901.4 1111.03  5937.4 1113.24
  5943.4 1112.66  5964.4 1113.51  6022.2 1116.79  6108.8 1120.47  6130.8 1121.72
#Mann= 4 ,-1 , 0
  4627.3     .05       0  4980.4     .05       0  4992.5     .05       0
  6108.8     .12       0
#XS Ineff= 2 , 0
                         5072.73         1088.15
Permanent Ineff=
       F       F
Bank Sta=4980.4,4984.4
XS Rating Curve= 0 ,0
Exp/Cntr=0.3,0.1

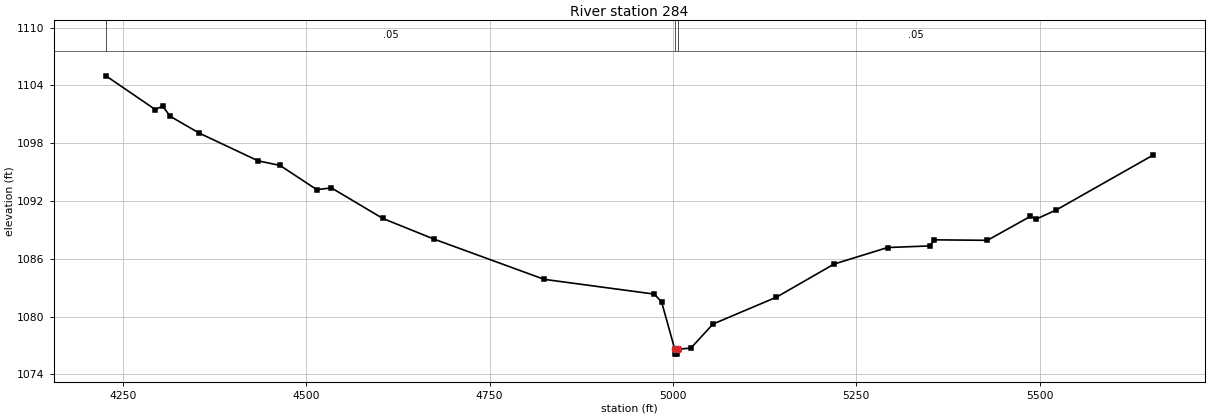
Type RM Length L Ch R = 1 ,284     ,0,0,0
BEGIN DESCRIPTION:
SANFERNANDO028 1.0
END DESCRIPTION:
XS GIS Cut Line= 3
      2798427.44     10228665.74      2798430.68     10229528.11
      2798906.62     10229832.45
#Sta/Elev= 30
  4227.1 1104.99  4294.5 1101.49  4304.5 1101.86  4314.5  1100.8  4354.5 1099.04
  4434.5 1096.17  4464.5 1095.69  4514.5 1093.18  4534.5 1093.36  4604.5 1090.19
  4674.5 1088.04  4824.5 1083.87  4974.5 1082.34  4984.5 1081.54  5002.5 1076.61
  5002.7 1076.11  5006.2 1076.11  5006.5 1076.61  5024.5 1076.74  5054.5 1079.23
  5141.1 1082.02  5219.7 1085.46  5292.5 1087.17    5350 1087.34  5356.5 1087.97
  5428.6 1087.92  5487.1  1090.4  5495.4 1090.13  5522.7 1091.08  5654.4 1096.76
#Mann= 3 ,-1 , 0
  4227.1     .05       0  5002.5     .05       0  5006.5     .05       0
Bank Sta=5002.5,5006.5
XS Rating Curve= 0 ,0
Exp/Cntr=0.3,0.1

Chan Stop Cuts=-1
Use User Specified Reach Order=0
Composite Channel Slope=5