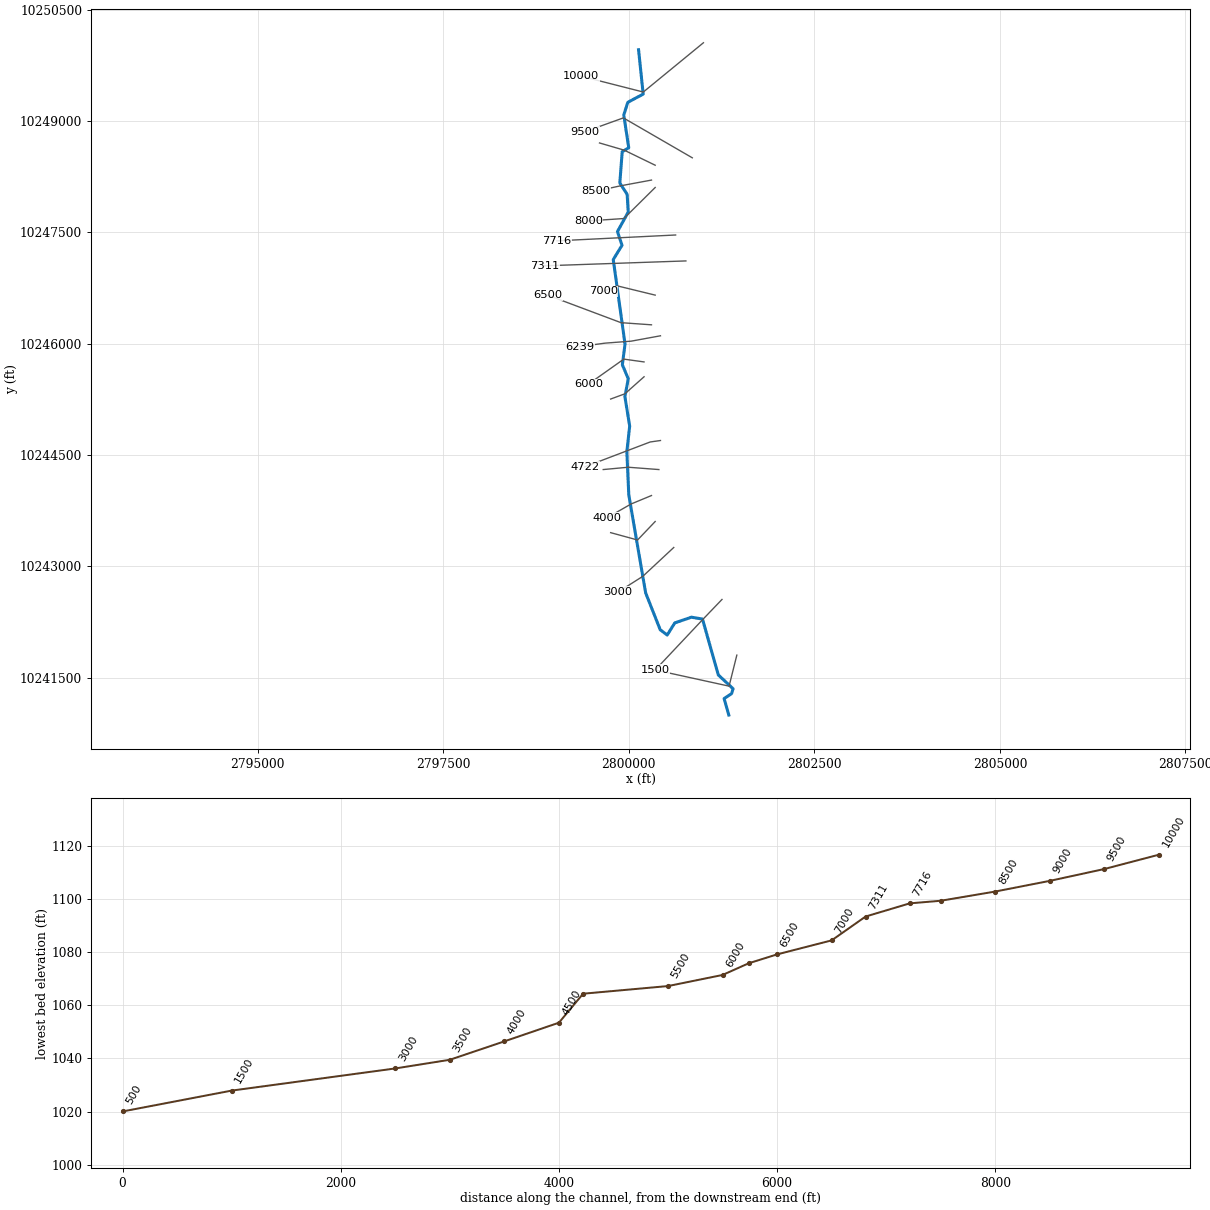
--- SANFERNANDO029.prj (project) ---

Proj Title=SANFERNANDO029 Base Level Engineering
Current Plan=p01
Default Exp/Contr=0.3,0.1
English Units
Geom File=g01
Flow File=f01
Plan File=p01
BEGIN DESCRIPTION:
SANFERNANDO029
END DESCRIPTION:

--- SANFERNANDO029.p01 (plan) ---

Plan Title=Multiple Run
Short Identifier=Multiple
Geom File=g01
Flow File=f01
Subcritical Flow
K Sum by GR= 0
Std Step Tol= 0.01
Critical Tol= 0.01
Num of Std Step Trials= 20
Max Error Tol= 0.3
Flow Tol Ratio= 0.001
Split Flow NTrial= 30
Split Flow Tol= 0.02
Split Flow Ratio= 0.02
Log Output Level= 0
Friction Slope Method= 1
Unsteady Friction Slope Method= 2
Unsteady Bridges Friction Slope Method= 1
Parabolic Critical Depth
Global Vel Dist=  1 , 1 , 1
Global Log Level= 0
CheckData=True
Encroach Param= -1, 0, 0, 0
BEGIN DESCRIPTION:
Multiple Run
END DESCRIPTION:

--- SANFERNANDO029.f01 (steady flow) ---

Flow Title=Multiple
Number of Profiles=7
Profile Names=10-year,25-year,50-year,1pct_min,100-year,1pct_plu,500-year
River Rch & RM= SANFERNANDO029,Reach-1,10000
     408     663     782     547    1030    1939    1411
River Rch & RM= SANFERNANDO029,Reach-1,1500
     767    1280    1811    1120    2456    5386    3345
Boundary for River Rch & Prof#=SANFERNANDO029,Reach-1,1
Up Type=0
Dn Type=3
Dn Slope=0.005
Boundary for River Rch & Prof#=SANFERNANDO029,Reach-1,2
Up Type=0
Dn Type=3
Dn Slope=0.005
Boundary for River Rch & Prof#=SANFERNANDO029,Reach-1,3
Up Type=0
Dn Type=3
Dn Slope=0.005
Boundary for River Rch & Prof#=SANFERNANDO029,Reach-1,4
Up Type=0
Dn Type=3
Dn Slope=0.005
Boundary for River Rch & Prof#=SANFERNANDO029,Reach-1,5
Up Type=0
Dn Type=3
Dn Slope=0.005
Boundary for River Rch & Prof#=SANFERNANDO029,Reach-1,6
Up Type=0
Dn Type=3
Dn Slope=0.005
Boundary for River Rch & Prof#=SANFERNANDO029,Reach-1,7
Up Type=0
Dn Type=3
Dn Slope=0.005

--- SANFERNANDO029.g01 (geometry) ---

Geom Title=Existing Conditions

River Reach=SANFERNANDO029,Reach-1
Reach XY= 30
      2800131.75     10249959.00      2800194.00     10249361.00
      2799987.00     10249251.00      2799932.25     10249080.00
      2799999.50     10248639.00      2799911.00     10248584.00
      2799879.25     10248163.00      2799978.00     10248011.00
      2799992.50     10247772.00      2799847.25     10247509.00
      2799909.25     10247325.00      2799790.75     10247132.00
      2799949.50     10245993.00      2799913.25     10245715.00
      2799993.00     10245526.00      2799947.75     10245285.00
      2800012.00     10244889.00      2799974.00     10244544.00
      2800000.00     10243962.00      2800227.25     10242641.00
      2800423.50     10242145.00      2800517.25     10242074.00
      2800619.75     10242237.00      2800843.75     10242314.00
      2800993.00     10242289.00      2801206.00     10241536.00
      2801405.25     10241350.00      2801384.75     10241284.00
      2801284.00     10241218.00      2801347.50     10240996.00

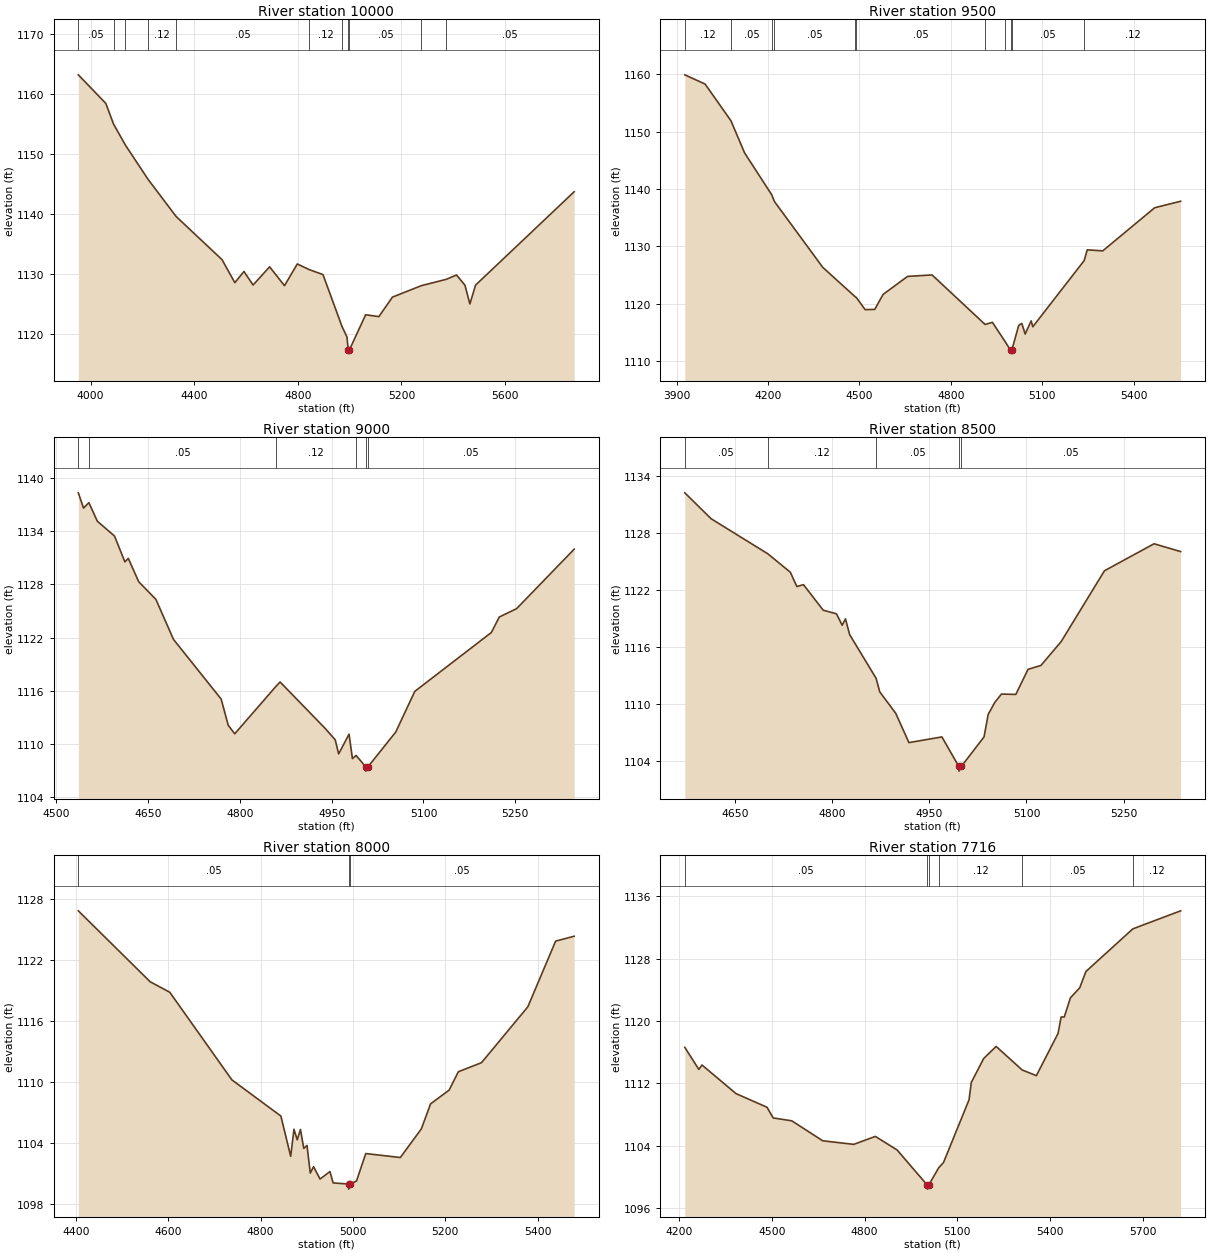
Type RM Length L Ch R = 1,10000,500,500,500
BEGIN DESCRIPTION:
SANFERNANDO029 20.0
END DESCRIPTION:
XS GIS Cut Line= 3
      2801005.67     10250053.10      2800195.64     10249389.10
      2799355.67     10249603.11
#Sta/Elev= 30
  3952.6 1163.13  4058.8 1158.37  4088.4 1154.95  4134.2 1151.44  4221.8 1145.73
  4330.4 1139.53  4507.3 1132.36  4556.9 1128.52  4592.0 1130.39  4627.2 1128.13
  4691.1 1131.16  4748.5 1128.02  4798.0 1131.64  4843.7 1130.70  4897.1 1129.87
  4970.9 1121.19  4989.6 1119.50  4994.7 1117.29  4995.0 1116.79  4998.7 1117.29
  5061.9 1123.18  5112.9 1122.87  5165.1 1126.11  5277.2 1128.03  5372.5 1129.07
  5412.7 1129.80  5445.2 1128.10  5464.3 1124.98  5486.1 1128.11  5866.8 1143.66
#Mann=11,-1,0
  3952.6    0.05       0  4088.4    0.12       0  4134.2    0.05       0
  4221.8    0.12       0  4330.4    0.05       0  4843.7    0.12       0
  4970.9    0.05       0  4994.7    0.05       0  4998.7    0.05       0
  5277.2    0.12       0  5372.5    0.05       0
Bank Sta=4994.7,4998.7
Exp/Cntr=0.3,0.1

Type RM Length L Ch R = 1,9500,500,500,500
BEGIN DESCRIPTION:
SANFERNANDO029 19.0
END DESCRIPTION:
XS GIS Cut Line= 3
      2800855.72     10248503.09      2799927.00     10249040.90
      2799405.69     10248853.11
#Sta/Elev= 30
  3926.8 1159.90  3993.5 1158.29  4078.1 1151.91  4123.3 1146.27  4212.3 1138.98
  4220.9 1137.83  4379.6 1126.35  4486.3 1121.21  4489.7 1121.10  4518.7 1118.98
  4550.2 1119.02  4577.6 1121.63  4657.9 1124.77  4738.3 1125.03  4912.5 1116.39
  4936.3 1116.77  4978.6 1113.37  4995.9 1111.90  4996.1 1111.40  4999.9 1111.90
  5022.7 1116.22  5032.8 1116.59  5043.9 1114.73  5063.5 1117.02  5068.9 1115.99
  5237.6 1127.53  5247.7 1129.40  5298.5 1129.22  5469.1 1136.74  5554.1 1137.87
#Mann=11,-1,0
  3926.8    0.12       0  4078.1    0.05       0  4212.3    0.12       0
  4220.9    0.05       0  4486.3    0.12       0  4489.7    0.05       0
  4912.5    0.12       0  4978.6    0.05       0  4995.9    0.05       0
  4999.9    0.05       0  5237.6    0.12       0
Bank Sta=4995.9,4999.9
Exp/Cntr=0.3,0.1

Type RM Length L Ch R = 1,9000,500,500,500
BEGIN DESCRIPTION:
SANFERNANDO029 18.0
END DESCRIPTION:
XS GIS Cut Line= 3
      2800355.66     10248403.12      2799938.19     10248606.09
      2799605.66     10248703.12
#Sta/Elev= 30
  4535.8 1138.33  4544.3 1136.61  4553.1 1137.22  4566.8 1135.13  4594.9 1133.46
  4611.9 1130.54  4617.5 1130.93  4634.5 1128.30  4662.6 1126.31  4691.4 1121.79
  4769.3 1115.06  4780.9 1112.10  4791.5 1111.14  4858.6 1116.47  4865.6 1116.99
  4938.8 1111.79  4955.8 1110.46  4961.4 1108.87  4978.4 1111.10  4983.9 1108.34
  4989.9 1108.70  5005.5 1107.43  5005.8 1106.93  5009.5 1107.43  5054.7 1111.34
  5085.9 1115.93  5211.0 1122.57  5224.0 1124.32  5252.3 1125.26  5346.4 1131.97
#Mann=6,-1,0
  4535.8    0.12       0  4553.1    0.05       0  4858.6    0.12       0
  4989.9    0.05       0  5005.5    0.05       0  5009.5    0.05       0
Bank Sta=5005.5,5009.5
Exp/Cntr=0.3,0.1

Type RM Length L Ch R = 1,8500,500,500,500
BEGIN DESCRIPTION:
SANFERNANDO029 17.0
END DESCRIPTION:
XS GIS Cut Line= 3
      2800305.72     10248203.12      2799885.69     10248125.17
      2799555.66     10248053.11
#Sta/Elev= 30
  4572.8 1132.19  4613.5 1129.46  4700.8 1125.78  4735.6 1123.84  4745.7 1122.33
  4755.9 1122.53  4786.4 1119.84  4806.8 1119.46  4815.6 1118.26  4820.7 1118.93
  4827.1 1117.28  4868.0 1112.67  4873.6 1111.25  4898.3 1108.99  4918.6 1105.91
  4969.5 1106.51  4995.5 1103.41  4995.7 1102.91  4999.5 1103.41  5034.5 1106.51
  5040.9 1108.88  5051.2 1110.15  5061.4 1111.02  5083.5 1110.98  5102.4 1113.62
  5122.3 1114.03  5153.5 1116.54  5220.3 1123.99  5296.8 1126.83  5337.8 1126.01
#Mann=5,-1,0
  4572.8    0.05       0  4700.8    0.12       0  4868.0    0.05       0
  4995.5    0.05       0  4999.5    0.05       0
Bank Sta=4995.5,4999.5
Exp/Cntr=0.3,0.1

Type RM Length L Ch R = 1,8000,284,284,284
BEGIN DESCRIPTION:
SANFERNANDO029 16.0
END DESCRIPTION:
XS GIS Cut Line= 3
      2800355.67     10248103.10      2799933.40     10247684.90
      2799455.66     10247653.11
#Sta/Elev= 30
  4405.7 1126.81  4561.2 1119.83  4603.6 1118.80  4738.0 1110.18  4844.1 1106.62
  4865.3 1102.66  4872.4 1105.32  4879.5 1104.28  4886.5 1105.30  4893.6 1103.44
  4900.6 1103.73  4907.7 1101.01  4914.8 1101.64  4928.9 1100.42  4950.2 1101.16
  4957.2 1100.04  4990.6 1099.93  4990.8 1099.43  4994.6 1099.93  5007.7 1100.23
  5027.8 1102.93  5102.6 1102.54  5148.0 1105.35  5168.1 1107.82  5208.2 1109.17
  5228.2 1110.98  5278.3 1111.87  5378.6 1117.37  5438.7 1123.83  5478.8 1124.31
#Mann=3,-1,0
  4405.7    0.05       0  4990.6    0.05       0  4994.6    0.05       0
Bank Sta=4990.6,4994.6
Exp/Cntr=0.3,0.1

Type RM Length L Ch R = 1,7716,405,405,405
BEGIN DESCRIPTION:
Mapping XS c9866f62
END DESCRIPTION:
XS GIS Cut Line= 2
      2800631.12     10247463.31      2799029.87     10247384.24
#Sta/Elev= 30
  4218.8 1116.63  4264.3 1113.80  4274.3 1114.37  4384.4 1110.70  4484.6 1108.95
  4504.6 1107.58  4564.7 1107.21  4664.8 1104.65  4764.9 1104.19  4835.0 1105.21
  4905.1 1103.48  5003.2 1098.95  5003.4 1098.45  5007.2 1098.95  5039.8 1101.19
  5055.3 1101.86  5137.8 1109.90  5145.4 1112.15  5185.4 1115.21  5225.5 1116.75
  5309.7 1113.73  5355.6 1113.00  5425.7 1118.42  5435.7 1120.53  5445.7 1120.52
  5465.8 1122.99  5495.8 1124.27  5515.8 1126.36  5667.6 1131.83  5822.0 1134.14
#Mann=6,-1,0
  4218.8    0.05       0  5003.2    0.05       0  5007.2    0.05       0
  5039.8    0.12       0  5309.7    0.05       0  5667.6    0.12       0
Bank Sta=5003.2,5007.2
Exp/Cntr=0.3,0.1

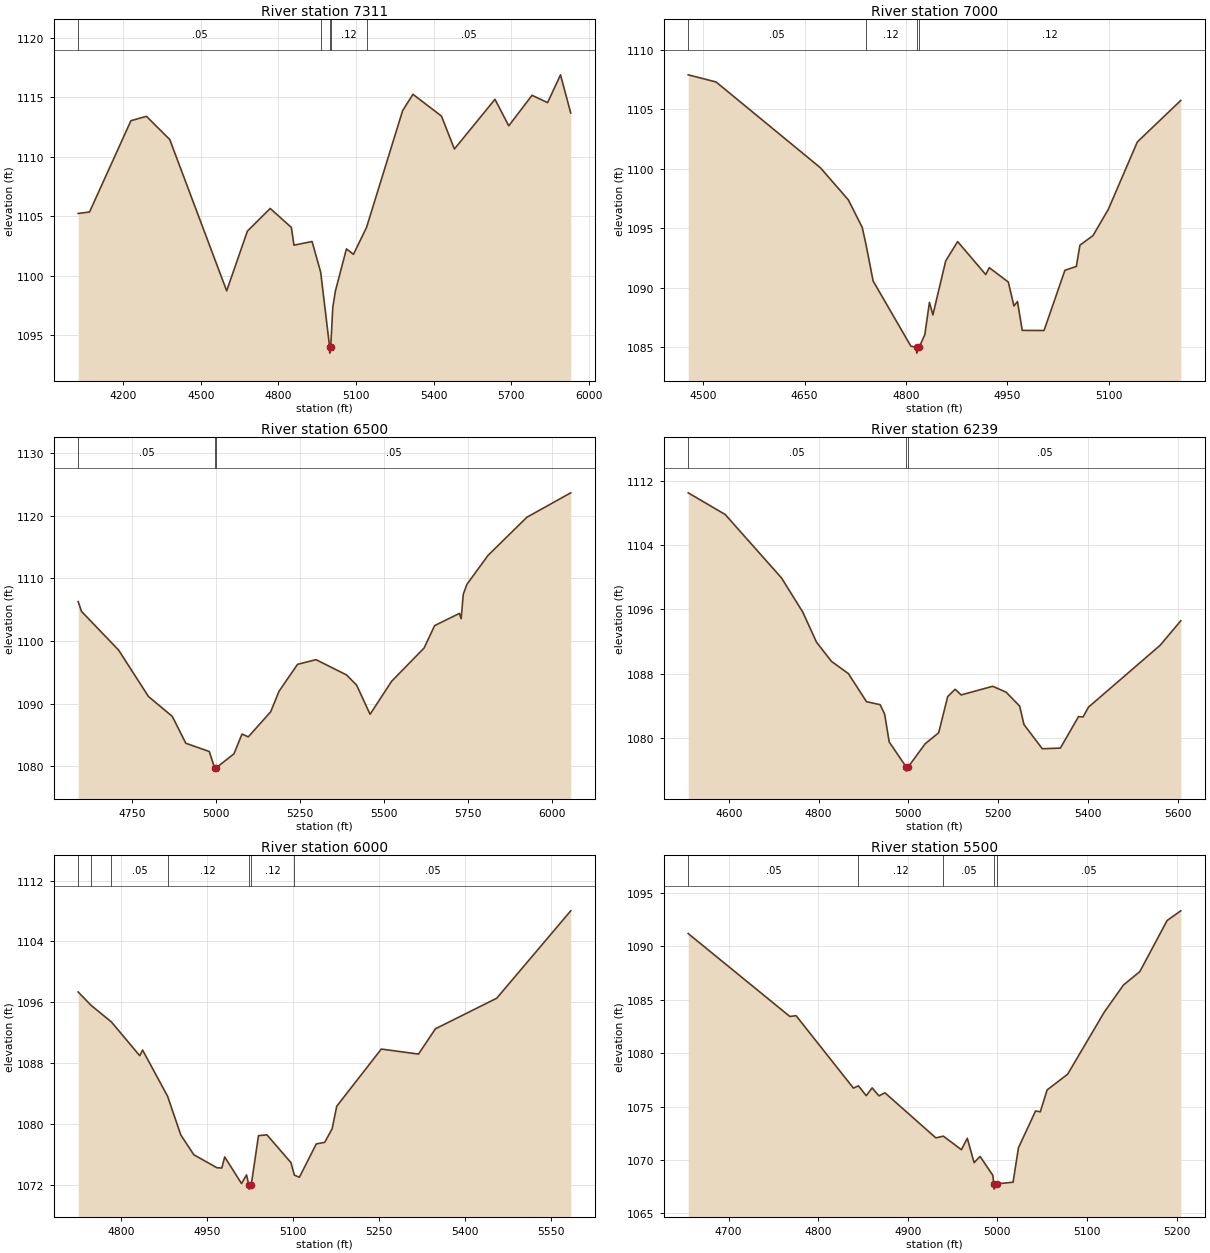
Type RM Length L Ch R = 1,7311,311,311,311
BEGIN DESCRIPTION:
Mapping XS c133f086
END DESCRIPTION:
XS GIS Cut Line= 2
      2800769.55     10247113.91      2798866.19     10247048.05
#Sta/Elev= 30
  4025.7 1105.23  4069.6 1105.35  4229.7 1113.03  4289.7 1113.40  4379.8 1111.45
  4599.9 1098.72  4680.0 1103.74  4768.3 1105.65  4850.1 1104.05  4860.1 1102.56
  4930.1 1102.87  4963.4 1100.29  4998.1 1093.98  4998.4 1093.48  5002.1 1093.98
  5010.2 1097.32  5020.2 1098.70  5063.0 1102.25  5090.2 1101.79  5140.8 1104.06
  5280.3 1113.88  5320.3 1115.25  5430.4 1113.42  5480.4 1110.65  5637.3 1114.83
  5690.6 1112.60  5780.6 1115.17  5840.7 1114.55  5890.7 1116.89  5930.2 1113.68
#Mann=5,-1,0
  4025.7    0.05       0  4963.4    0.12       0  4998.1    0.07       0
  5002.1    0.12       0  5140.8    0.05       0
Bank Sta=4998.1,5002.1
Exp/Cntr=0.3,0.1

Type RM Length L Ch R = 1,7000,500,500,500
BEGIN DESCRIPTION:
SANFERNANDO029 14.0
END DESCRIPTION:
XS GIS Cut Line= 3
      2800355.70     10246653.11      2799848.39     10246776.94
      2799655.65     10246703.10
#Sta/Elev= 30
  4477.8 1107.88  4519.0 1107.28  4673.4 1100.07  4714.7 1097.37  4735.2 1095.06
  4741.0 1093.56  4751.3 1090.56  4807.2 1085.08  4815.5 1085.00  4815.8 1084.50
  4819.5 1085.00  4827.8 1086.06  4834.6 1088.77  4839.7 1087.71  4858.7 1092.25
  4876.3 1093.87  4917.9 1091.10  4923.1 1091.68  4951.3 1090.47  4959.6 1088.46
  4964.8 1088.84  4971.9 1086.41  5004.1 1086.40  5035.0 1091.46  5051.9 1091.78
  5057.2 1093.57  5076.5 1094.37  5099.3 1096.59  5142.1 1102.24  5206.4 1105.73
#Mann=4,-1,0
  4477.8    0.05       0  4741.0    0.12       0  4815.5    0.07       0
  4819.5    0.12       0
Bank Sta=4815.5,4819.5
Exp/Cntr=0.3,0.1

Type RM Length L Ch R = 1,6500,261,261,261
BEGIN DESCRIPTION:
SANFERNANDO029 13.0
END DESCRIPTION:
XS GIS Cut Line= 3
      2800305.67     10246253.11      2799895.28     10246282.00
      2798905.68     10246653.11
#Sta/Elev= 30
  4588.6 1106.27  4598.6 1104.70  4708.9 1098.55  4798.1 1091.13  4869.3 1087.95
  4909.4 1083.67  4979.5 1082.35  4995.3 1079.72  4995.5 1079.22  4999.3 1079.72
  5053.0 1081.98  5077.0 1085.14  5095.7 1084.68  5162.5 1088.69  5187.4 1091.97
  5242.6 1096.26  5297.7 1097.00  5388.5 1094.57  5418.8 1092.93  5458.8 1088.29
  5522.9 1093.55  5619.9 1098.87  5651.1 1102.43  5724.9 1104.38  5730.3 1103.55
  5736.5 1107.42  5747.2 1109.00  5810.4 1113.64  5926.1 1119.72  6056.9 1123.62
#Mann=3,-1,0
  4588.6    0.05       0  4995.3    0.03       0  4999.3    0.05       0
Bank Sta=4995.3,4999.3
Exp/Cntr=0.3,0.1

Type RM Length L Ch R = 1,6239,239,239,239
BEGIN DESCRIPTION:
Mapping XS 409f27ec
END DESCRIPTION:
XS GIS Cut Line= 4
      2800426.75     10246105.25      2800031.19     10246032.73
      2799681.79     10246006.36      2799339.82     10245960.32
#Sta/Elev= 30
  4509.5 1110.53  4591.9 1107.83  4717.2 1099.94  4764.8 1095.67  4795.3 1091.93
  4828.6 1089.54  4866.4 1088.01  4906.8 1084.51  4937.2 1084.14  4947.3 1082.94
  4957.3 1079.50  4995.4 1076.36  4995.7 1075.86  4999.4 1076.36  5037.5 1079.27
  5067.6 1080.64  5087.7 1085.15  5104.3 1086.06  5117.7 1085.35  5187.9 1086.43
  5218.0 1085.69  5248.1 1083.96  5257.6 1081.67  5298.5 1078.65  5338.8 1078.73
  5379.2 1082.65  5389.3 1082.61  5401.6 1083.84  5560.8 1091.52  5607.1 1094.59
#Mann=3,-1,0
  4509.5    0.05       0  4995.4    0.03       0  4999.4    0.05       0
Bank Sta=4995.4,4999.4
Exp/Cntr=0.3,0.1

Type RM Length L Ch R = 1,6000,500,500,500
BEGIN DESCRIPTION:
SANFERNANDO029 12.0
END DESCRIPTION:
XS GIS Cut Line= 3
      2800205.68     10245753.11      2799933.00     10245791.00
      2799455.69     10245453.11
#Sta/Elev= 30
  4724.7 1097.36  4747.2 1095.61  4782.8 1093.42  4832.2 1088.99  4837.2 1089.73
  4880.8 1083.67  4903.9 1078.58  4926.6 1075.98  4967.0 1074.27  4975.5 1074.23
  4980.6 1075.69  5010.0 1072.19  5018.7 1073.33  5022.8 1071.96  5023.1 1071.46
  5026.8 1071.96  5039.6 1078.49  5054.4 1078.59  5096.2 1074.95  5102.2 1073.30
  5111.0 1073.02  5140.5 1077.40  5155.3 1077.61  5168.2 1079.40  5176.2 1082.35
  5254.0 1089.86  5319.0 1089.20  5348.5 1092.52  5455.6 1096.54  5584.8 1108.02
#Mann=7,-1,0
  4724.7    0.05       0  4747.2    0.12       0  4782.8    0.05       0
  4880.8    0.12       0  5022.8    0.07       0  5026.8    0.12       0
  5102.2    0.05       0
Bank Sta=5022.8,5026.8
Exp/Cntr=0.3,0.1

Type RM Length L Ch R = 1,5500,778,778,778
BEGIN DESCRIPTION:
SANFERNANDO029 11.0
END DESCRIPTION:
XS GIS Cut Line= 3
      2800205.72     10245553.14      2799947.75     10245323.92
      2799755.69     10245253.11
#Sta/Elev= 30
  4654.9 1091.21  4768.3 1083.45  4775.3 1083.52  4839.3 1076.74  4844.9 1076.95
  4853.6 1076.03  4860.2 1076.76  4867.8 1076.01  4874.5 1076.30  4931.3 1072.08
  4939.7 1072.24  4959.8 1070.97  4966.4 1072.04  4974.0 1069.76  4980.7 1070.34
  4994.9 1068.57  4996.0 1067.78  4996.3 1067.28  5000.0 1067.78  5017.5 1067.93
  5023.5 1071.15  5042.6 1074.60  5047.9 1074.52  5055.5 1076.57  5078.4 1078.04
  5119.4 1083.87  5140.8 1086.40  5159.0 1087.65  5189.5 1092.44  5204.7 1093.34
#Mann=5,-1,0
  4654.9    0.05       0  4844.9    0.12       0  4939.7    0.05       0
  4996.0    0.05       0  5000.0    0.05       0
Bank Sta=4996,5000
Exp/Cntr=0.3,0.1

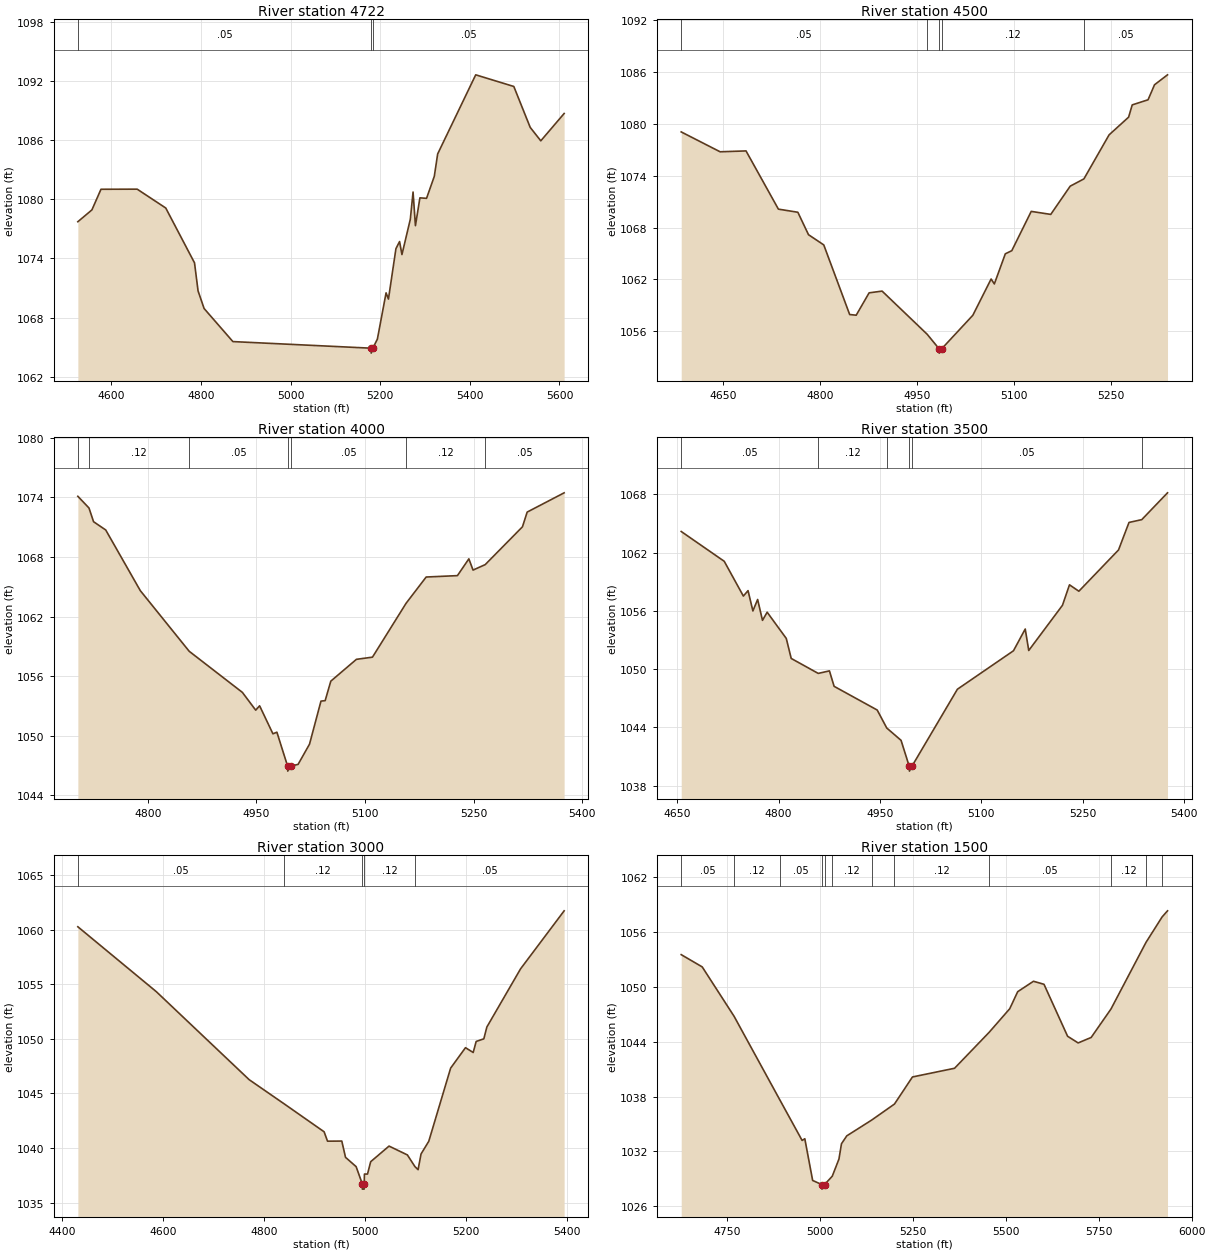
Type RM Length L Ch R = 1,4722,222,222,222
BEGIN DESCRIPTION:
Mapping XS 202ea16f
END DESCRIPTION:
XS GIS Cut Line= 3
      2800426.73     10244694.43      2800288.30     10244674.66
      2799404.95     10244338.46
#Sta/Elev= 30
  4525.4 1077.72  4556.8 1078.92  4577.0 1081.01  4657.8 1081.02  4721.5 1079.11
  4785.7 1073.55  4793.6 1070.71  4807.1 1068.92  4871.3 1065.57  5179.6 1064.90
  5179.9 1064.40  5183.6 1064.90  5193.7 1065.82  5213.1 1070.51  5218.4 1069.88
  5235.1 1074.99  5243.2 1075.71  5248.5 1074.39  5267.2 1077.97  5273.3 1080.73
  5278.6 1077.32  5288.6 1080.14  5303.4 1080.09  5320.7 1082.32  5328.2 1084.59
  5413.1 1092.61  5498.1 1091.43  5534.7 1087.28  5558.3 1085.92  5610.4 1088.69
#Mann=3,-1,0
  4525.4    0.05       0  5179.6    0.03       0  5183.6    0.05       0
Bank Sta=5179.6,5183.6
Exp/Cntr=0.3,0.1

Type RM Length L Ch R = 1,4500,500,500,500
BEGIN DESCRIPTION:
SANFERNANDO029 9.0
END DESCRIPTION:
XS GIS Cut Line= 3
      2800405.67     10244303.11      2799992.36     10244334.44
      2799655.71     10244303.11
#Sta/Elev= 30
  4585.5 1079.08  4645.7 1076.78  4685.8 1076.88  4735.9 1070.14  4766.0 1069.78
  4782.5 1067.18  4806.1 1066.00  4846.2 1057.94  4856.3 1057.86  4876.3 1060.45
  4896.4 1060.65  4966.2 1055.65  4984.6 1053.97  4984.9 1053.47  4988.6 1053.97
  5036.8 1057.85  5065.1 1062.05  5070.1 1061.48  5087.1 1064.97  5097.1 1065.33
  5127.2 1069.88  5157.4 1069.53  5187.5 1072.80  5208.7 1073.64  5247.7 1078.74
  5277.9 1080.79  5283.5 1082.21  5308.0 1082.80  5318.0 1084.54  5338.1 1085.69
#Mann=5,-1,0
  4585.5    0.05       0  4966.2    0.12       0  4984.6    0.07       0
  4988.6    0.12       0  5208.7    0.05       0
Bank Sta=4984.6,4988.6
Exp/Cntr=0.3,0.1

Type RM Length L Ch R = 1,4000,500,500,500
BEGIN DESCRIPTION:
SANFERNANDO029 8.0
END DESCRIPTION:
XS GIS Cut Line= 3
      2800305.69     10243953.11      2800031.45     10243839.36
      2799705.72     10243653.13
#Sta/Elev= 30
  4703.1 1074.12  4718.5 1072.94  4724.8 1071.56  4741.6 1070.73  4789.4 1064.62
  4857.0 1058.51  4930.5 1054.37  4948.9 1052.58  4954.3 1053.02  4972.7 1050.20
  4978.2 1050.36  4993.0 1046.94  4993.2 1046.44  4997.0 1046.94  5007.5 1047.12
  5023.3 1049.16  5039.1 1053.49  5044.9 1053.54  5052.7 1055.50  5088.1 1057.70
  5110.3 1057.92  5156.8 1063.35  5184.5 1065.99  5227.7 1066.13  5243.5 1067.82
  5249.3 1066.69  5266.1 1067.24  5317.6 1071.05  5324.1 1072.53  5375.2 1074.47
#Mann=7,-1,0
  4703.1    0.05       0  4718.5    0.12       0  4857.0    0.05       0
  4993.0    0.05       0  4997.0    0.05       0  5156.8    0.12       0
  5266.1    0.05       0
Bank Sta=4993,4997
Exp/Cntr=0.3,0.1

Type RM Length L Ch R = 1,3500,500,500,500
BEGIN DESCRIPTION:
SANFERNANDO029 7.0
END DESCRIPTION:
XS GIS Cut Line= 3
      2800355.68     10243603.11      2800118.15     10243354.14
      2799755.71     10243453.10
#Sta/Elev= 30
  4655.9 1064.17  4719.6 1061.10  4747.9 1057.52  4754.8 1058.08  4762.0 1055.99
  4769.0 1057.17  4776.2 1055.02  4783.1 1055.86  4811.4 1053.16  4818.7 1051.10
  4858.7 1049.56  4875.3 1049.82  4882.2 1048.23  4946.0 1045.79  4960.1 1043.94
  4981.3 1042.67  4993.4 1040.00  4993.7 1039.50  4997.4 1040.00  5064.7 1047.93
  5147.7 1051.89  5165.1 1054.13  5170.3 1051.92  5220.2 1056.57  5230.6 1058.68
  5244.5 1058.02  5303.2 1062.27  5318.7 1065.10  5337.6 1065.39  5375.7 1068.15
#Mann=6,-1,0
  4655.9    0.05       0  4858.7    0.12       0  4960.1    0.05       0
  4993.4    0.05       0  4997.4    0.05       0  5337.6    0.12       0
Bank Sta=4993.4,4997.4
Exp/Cntr=0.3,0.1

Type RM Length L Ch R = 1,3000,1500,1500,1500
BEGIN DESCRIPTION:
SANFERNANDO029 6.0
END DESCRIPTION:
XS GIS Cut Line= 3
      2800605.71     10243253.14      2800189.06     10242864.89
      2799855.65     10242653.09
#Sta/Elev= 30
  4430.5 1060.25  4586.1 1054.31  4770.3 1046.25  4839.3 1044.05  4918.9 1041.48
  4925.7 1040.62  4954.0 1040.63  4961.4 1039.14  4982.4 1038.29  4994.5 1036.73
  4994.8 1036.23  4998.3 1036.23  4998.5 1036.73  4998.9 1037.61  5005.0 1037.61
  5011.3 1038.74  5047.7 1040.17  5084.1 1039.36  5099.1 1038.29  5105.3 1038.01
  5111.2 1039.45  5126.5 1040.61  5169.9 1047.31  5199.3 1049.18  5214.6 1048.74
  5220.5 1049.75  5235.7 1049.99  5241.7 1051.07  5308.6 1056.40  5395.0 1061.71
#Mann=5,-1,0
  4430.5    0.05       0  4839.3    0.12       0  4994.5    0.07       0
  4998.5    0.12       0  5099.1    0.05       0
Bank Sta=4994.5,4998.5
Exp/Cntr=0.3,0.1

Type RM Length L Ch R = 1,1500,1000,1000,1000
BEGIN DESCRIPTION:
SANFERNANDO029 3.0
END DESCRIPTION:
XS GIS Cut Line= 3
      2801255.71     10242553.14      2800996.90     10242283.57
      2800355.67     10241603.10
#Sta/Elev= 30
  4626.3 1053.51  4682.8 1052.17  4768.6 1046.77  4891.1 1037.68  4951.7 1033.20
  4958.9 1033.39  4980.0 1028.83  5004.5 1028.38  5005.0 1027.88  5012.1 1028.38
  5032.9 1029.30  5050.8 1031.17  5057.6 1032.84  5071.8 1033.70  5138.9 1035.43
  5200.2 1037.18  5248.6 1040.14  5361.9 1041.09  5455.0 1045.02  5510.4 1047.60
  5531.8 1049.46  5574.3 1050.60  5602.6 1050.27  5666.1 1044.59  5694.5 1043.86
  5729.6 1044.46  5782.9 1047.57  5877.1 1054.85  5920.6 1057.64  5935.0 1058.30
#Mann=12,-1,0
  4626.3    0.05       0  4768.6    0.12       0  4891.1    0.05       0
  5004.5    0.03       0  5012.1    0.05       0  5032.9    0.12       0
  5138.9    0.05       0  5200.2    0.12       0  5455.0    0.05       0
  5782.9    0.12       0  5877.1    0.05       0  5920.6    0.12       0
Bank Sta=5004.5,5012.1
Exp/Cntr=0.3,0.1

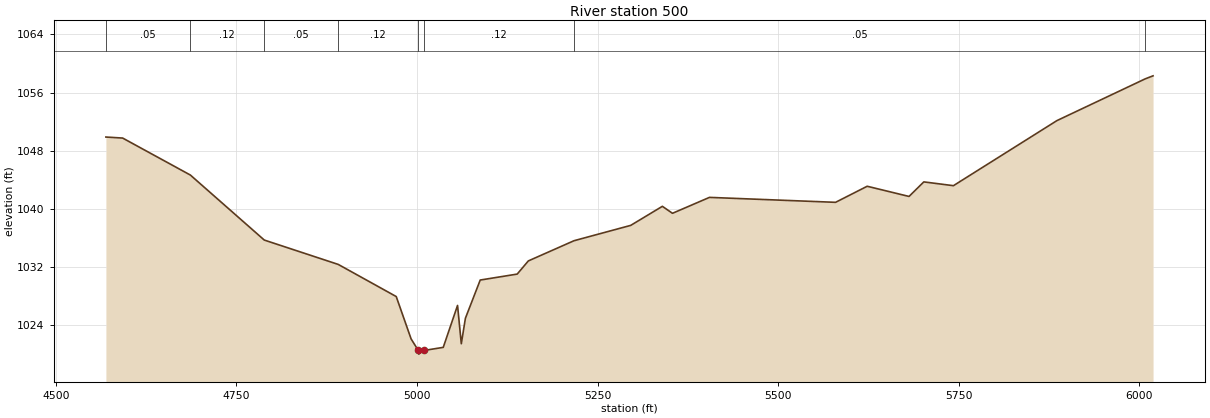
Type RM Length L Ch R = 1,500,0,0,0
BEGIN DESCRIPTION:
SANFERNANDO029 1.0
END DESCRIPTION:
XS GIS Cut Line= 3
      2801455.68     10241803.08      2801351.17     10241385.15
      2800355.65     10241603.12
#Sta/Elev= 30
  4569.2 1049.88  4592.4 1049.74  4686.2 1044.65  4788.5 1035.71  4890.9 1032.36
  4971.2 1027.94  4991.8 1022.11  5001.8 1020.52  5002.3 1020.02  5009.4 1020.52
  5036.3 1020.95  5056.1 1026.72  5061.3 1021.45  5067.0 1024.96  5087.5 1030.21
  5138.7 1031.03  5154.1 1032.84  5217.4 1035.62  5295.9 1037.73  5339.7 1040.35
  5353.7 1039.39  5404.9 1041.58  5579.5 1040.90  5623.3 1043.11  5681.2 1041.71
  5701.7 1043.71  5742.7 1043.19  5886.0 1052.14  6008.4 1057.89  6019.1 1058.30
#Mann=8,-1,0
  4569.2    0.05       0  4686.2    0.12       0  4788.5    0.05       0
  4890.9    0.12       0  5001.8    0.07       0  5009.4    0.12       0
  5217.4    0.05       0  6008.4    0.12       0
Bank Sta=5001.8,5009.4
Exp/Cntr=0.3,0.1

Chan Stop Cuts=-1