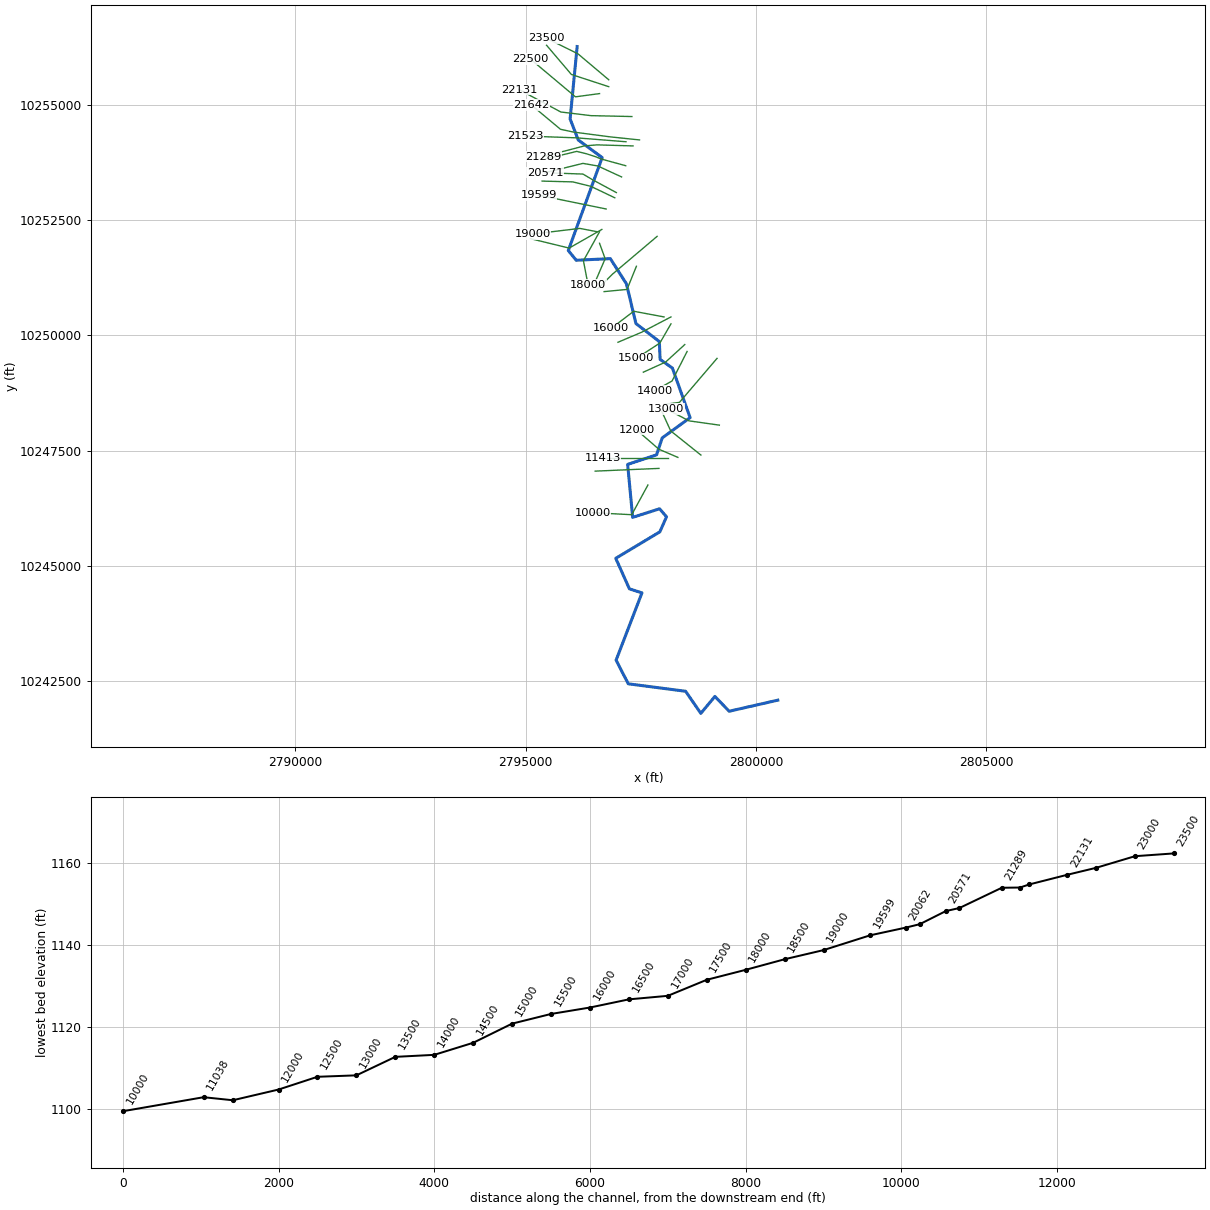
--- SANFERNANDO030.prj (project) ---

Proj Title=SANFERNANDO030 Base Level Engineering
Current Plan=p01
Default Exp/Contr=0.3,0.1
English Units
Geom File=g01
Flow File=f01
Plan File=p01
Y Axis Title=Elevation
X Axis Title(PF)=Main Channel Distance
X Axis Title(XS)=Station
BEGIN DESCRIPTION:
SANFERNANDO030
END DESCRIPTION:
DSS Export Rating Curves= 0
DSS Export Rating Curve Sorted= 0
DSS Export Volume Flow Curves= 0
DXF OffsetX= 0
DXF OffsetY= 0
DXF ScaleX= 1
DXF ScaleY= 10

--- SANFERNANDO030.p01 (plan) ---

Plan Title=Multiple Run
Short Identifier=Multiple
Geom File=g01
Flow File=f01
Subcritical Flow
K Sum by GR= 0
Std Step Tol= 0.01
Critical Tol= 0.01
Num of Std Step Trials= 20
Max Error Tol= 0.3
Flow Tol Ratio= 0.001
Split Flow NTrial= 30
Split Flow Tol= 0.02
Split Flow Ratio= 0.02
Log Output Level= 0
Friction Slope Method= 1
Unsteady Friction Slope Method= 2
Unsteady Bridges Friction Slope Method= 1
Parabolic Critical Depth
Global Vel Dist=  1 , 1 , 1
Global Log Level= 0
CheckData=True
Encroach Param= -1, 0, 0, 0
BEGIN DESCRIPTION:
Multiple Run
END DESCRIPTION:

--- SANFERNANDO030.f01 (steady flow) ---

Flow Title=Multiple
Number of Profiles=7
Profile Names=10-year,25-year,50-year,1pct_min,100-year,1pct_plu,500-year
River Rch & RM= SANFERNANDO030,Reach-1,23500
     422     681     749     456     819    1472    1075
River Rch & RM= SANFERNANDO030,Reach-1,16000
     934    1610    1771     949    2102    4658    2804
Boundary for River Rch & Prof#=SANFERNANDO030,Reach-1,1
Up Type=0
Dn Type=3
Dn Slope=0.005
Boundary for River Rch & Prof#=SANFERNANDO030,Reach-1,2
Up Type=0
Dn Type=3
Dn Slope=0.005
Boundary for River Rch & Prof#=SANFERNANDO030,Reach-1,3
Up Type=0
Dn Type=3
Dn Slope=0.005
Boundary for River Rch & Prof#=SANFERNANDO030,Reach-1,4
Up Type=0
Dn Type=3
Dn Slope=0.005
Boundary for River Rch & Prof#=SANFERNANDO030,Reach-1,5
Up Type=0
Dn Type=3
Dn Slope=0.005
Boundary for River Rch & Prof#=SANFERNANDO030,Reach-1,6
Up Type=0
Dn Type=3
Dn Slope=0.005
Boundary for River Rch & Prof#=SANFERNANDO030,Reach-1,7
Up Type=0
Dn Type=3
Dn Slope=0.005

--- SANFERNANDO030.g01 (geometry) ---

Geom Title=Existing Conditions
Program Version=4.10

River Reach=SANFERNANDO030  ,Reach-1
Reach XY= 30
      2796119.75       10256275.      2795967.25       10254702.
      2796143.75       10254246.      2796662.75       10253864.
       2795927.5       10251845.      2796099.75       10251634.
        2796840.       10251669.       2797189.5       10251122.
      2797394.75       10250260.      2797903.25       10249868.
      2797920.25       10249481.      2798187.25       10249292.
      2798571.25       10248216.      2797965.75       10247776.
       2797843.5       10247409.      2797215.75       10247201.
      2797324.75       10246051.      2797908.25       10246237.
      2798059.25       10246063.       2797914.5       10245736.
      2796957.25       10245161.      2797254.25       10244498.
        2797526.       10244411.      2796965.25       10242950.
        2797229.       10242436.      2798473.75       10242274.
      2798803.75       10241794.      2799109.25       10242162.
      2799418.25       10241840.        2800474.       10242081.

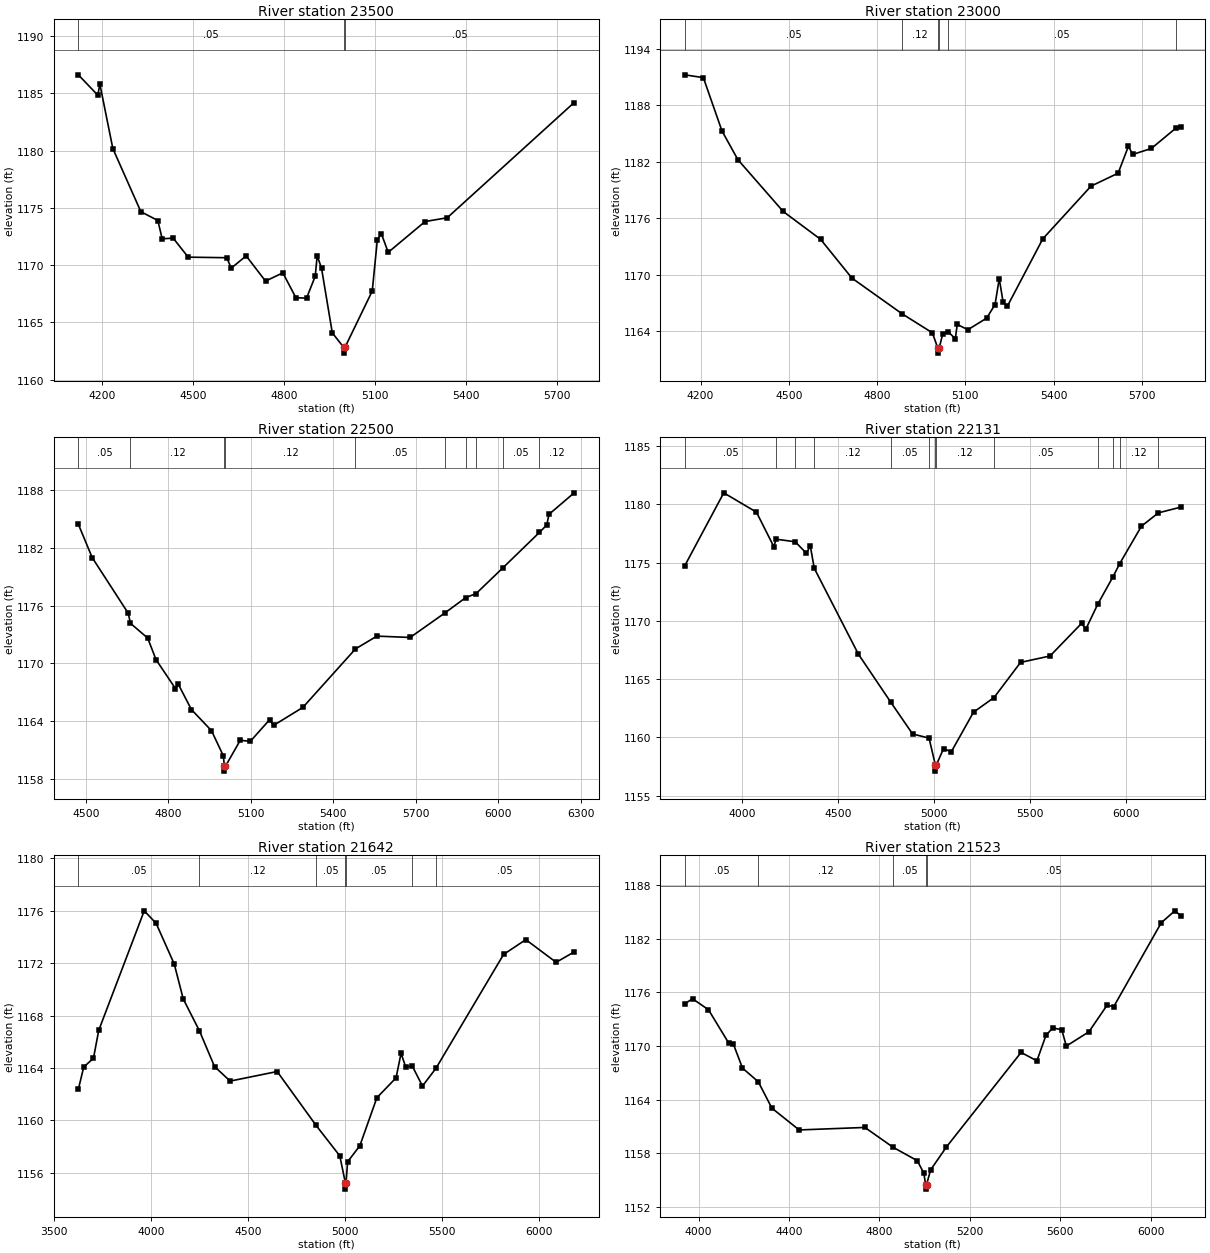
Type RM Length L Ch R = 1 ,23500   ,500,500,500
BEGIN DESCRIPTION:
SANFERNANDO030 47.0
END DESCRIPTION:
XS GIS Cut Line= 3
       2796805.7      10255553.1      2796134.95     10256118.73
      2795455.69     10256453.11
#Sta/Elev= 30
  4122.6 1186.62  4186.9 1184.84  4193.5 1185.82  4236.4 1180.18  4328.7 1174.67
  4384.7  1173.9    4399  1172.3  4435.3 1172.36  4484.7  1170.7  4612.2 1170.65
  4626.5 1169.74  4675.9 1170.81  4739.7 1168.61  4796.8 1169.33  4839.7 1167.16
  4874.9 1167.12  4903.5 1169.03    4910 1170.83  4924.3 1169.73  4959.8 1164.09
  4997.5 1162.82  4997.8 1162.32  5001.5 1162.82  5091.5 1167.74  5108.4 1172.24
  5121.8 1172.73  5144.1 1171.12  5265.7 1173.81  5338.7 1174.14  5757.1  1184.2
#Mann= 3 ,-1 , 0
  4122.6     .05       0  4997.5     .05       0  5001.5     .05       0
Bank Sta=4997.5,5001.5
XS Rating Curve= 0 ,0
Exp/Cntr=0.3,0.1

Type RM Length L Ch R = 1 ,23000   ,500,500,500
BEGIN DESCRIPTION:
SANFERNANDO030 46.0
END DESCRIPTION:
XS GIS Cut Line= 3
      2796805.68     10255403.11      2795994.39     10255668.82
      2795455.67     10256303.12
#Sta/Elev= 30
  4146.3 1191.24  4209.4 1190.94  4272.6 1185.28  4326.7 1182.22  4480.7 1176.71
  4608.1 1173.74  4714.5 1169.62  4884.8 1165.83  4988.1  1163.8    5007 1162.14
  5007.2 1161.64    5011 1162.14  5023.2 1163.67  5041.8 1163.91  5066.1 1163.17
  5072.7 1164.69  5108.9 1164.13  5172.6 1165.36  5201.2 1166.81  5215.5 1169.56
  5228.7 1167.05  5242.9 1166.62  5363.7  1173.8  5527.4  1179.4  5619.7 1180.78
  5654.8 1183.65  5669.1 1182.77  5732.8 1183.41  5816.8 1185.59  5832.2 1185.72
#Mann= 6 ,-1 , 0
  4146.3     .05       0  4884.8     .12       0    5007     .07       0
    5011     .12       0  5041.8     .05       0  5816.8     .12       0
Bank Sta=5007,5011
XS Rating Curve= 0 ,0
Exp/Cntr=0.3,0.1

Type RM Length L Ch R = 1 ,22500   ,369,369,369
BEGIN DESCRIPTION:
SANFERNANDO030 45.0
END DESCRIPTION:
XS GIS Cut Line= 3
      2796605.67     10255253.11      2796082.75     10255182.98
      2795105.72     10256003.08
#Sta/Elev= 30
  4472.4 1184.46  4522.8 1180.99    4654  1175.2  4661.9 1174.16  4724.6 1172.63
  4754.9 1170.39  4825.5 1167.38  4835.6 1167.85  4883.6  1165.2  4956.5 1163.01
    5000 1160.38  5003.3  1159.3  5003.6  1158.8  5007.3  1159.3  5061.4 1162.01
  5097.7 1161.89    5168 1164.14  5182.3 1163.55  5288.9 1165.42  5480.3  1171.5
  5558.2 1172.83  5679.2 1172.69  5805.6 1175.24  5881.7 1176.84  5918.6 1177.24
  6015.5  1179.9  6149.4 1183.61  6176.1 1184.38  6183.9 1185.48  6275.6 1187.72
#Mann= 10 ,-1 , 0
  4472.4     .05       0  4661.9     .12       0  5003.3     .07       0
  5007.3     .12       0  5480.3     .05       0  5805.6     .12       0
  5881.7     .05       0  5918.6     .12       0  6015.5     .05       0
  6149.4     .12       0
Bank Sta=5003.3,5007.3
XS Rating Curve= 0 ,0
Exp/Cntr=0.3,0.1

Type RM Length L Ch R = 1 ,22131   ,489,489,489
BEGIN DESCRIPTION:
Mapping XS 8a846cc1
END DESCRIPTION:
XS GIS Cut Line= 4
      2797308.43     10254754.68      2796418.47     10254774.46
      2795765.81     10254853.57      2794856.07      10255341.4
#Sta/Elev= 30
  3703.4 1174.74  3906.2 1180.99  4076.2 1179.33  4166.3 1176.38  4179.1 1177.01
    4278 1176.79  4336.3  1175.8  4356.3 1176.45  4376.9 1174.52  4606.5 1167.15
  4774.5 1163.04  4888.5  1160.3  4974.5 1159.94  5007.4 1157.61  5007.6 1157.11
  5011.4 1157.61  5049.7 1159.04    5090 1158.77  5205.7 1162.17  5312.3 1163.42
  5450.4 1166.44  5603.9 1166.99    5768 1169.79  5789.9 1169.29  5851.7 1171.42
  5931.1 1173.78  5966.5 1174.92  6079.5 1178.13  6167.5 1179.27  6283.3 1179.76
#Mann= 13 ,-1 , 0
  3703.4     .05       0  4179.1     .12       0    4278     .05       0
  4376.9     .12       0  4774.5     .05       0  4974.5     .12       0
  5007.4     .07       0  5011.4     .12       0  5312.3     .05       0
  5851.7     .12       0  5931.1     .05       0  5966.5     .12       0
  6167.5     .05       0
Bank Sta=5007.4,5011.4
XS Rating Curve= 0 ,0
Exp/Cntr=0.3,0.1

Type RM Length L Ch R = 1 ,21642   ,119,119,119
BEGIN DESCRIPTION:
Mapping XS da347343
END DESCRIPTION:
XS GIS Cut Line= 5
      2797473.32     10254247.05       2796840.4     10254312.98
       2796036.1     10254418.46      2795759.22      10254477.8
      2795126.36     10255005.18
#Sta/Elev= 30
  3626.2 1162.37    3654 1164.07  3704.3 1164.75  3731.2 1166.87  3965.7    1176
  4026.8 1175.05  4120.3 1171.94  4166.7 1169.27  4250.4 1166.83  4327.8 1164.11
  4408.5    1163  4650.6 1163.73  4851.4 1159.61  4973.3 1157.29  5001.6 1155.25
  5001.8 1154.75  5005.6 1155.25  5013.6 1156.84  5076.5 1158.06  5164.3 1161.73
  5263.2 1163.25  5288.9 1165.13  5312.6 1164.08  5346.6 1164.15  5399.2 1162.62
  5469.3 1163.99  5817.1 1172.67  5931.6  1173.8  6087.8 1172.07  6180.7 1172.86
#Mann= 7 ,-1 , 0
  3626.2     .05       0  4250.4     .12       0  4851.4     .05       0
  5001.6     .03       0  5005.6     .05       0  5346.6     .12       0
  5469.3     .05       0
Bank Sta=5001.6,5005.6
XS Rating Curve= 0 ,0
Exp/Cntr=0.3,0.1

Type RM Length L Ch R = 1 ,21523   ,234,234,234
BEGIN DESCRIPTION:
Mapping XS 7d8065ac
END DESCRIPTION:
XS GIS Cut Line= 3
      2797180.07     10254207.43      2796104.63     10254292.33
      2794990.12     10254331.93
#Sta/Elev= 30
  3938.9 1174.74  3973.4 1175.29  4043.6 1174.07  4133.9 1170.31    4154 1170.22
  4194.1 1167.54  4264.1 1166.01  4324.1 1163.06  4444.9 1160.62  4735.8  1160.9
  4860.6 1158.68  4967.8 1157.18  4996.6 1155.78  5004.6  1154.5  5004.8    1154
  5008.6  1154.5  5026.6 1156.15  5096.7 1158.72  5426.9 1169.29  5496.9 1168.35
    5537  1171.2    5567 1172.03    5607 1171.83    5627    1170  5727.1  1171.6
  5807.1 1174.56  5837.1 1174.42  6047.3  1183.8  6107.3 1185.13  6132.9  1184.6
#Mann= 5 ,-1 , 0
  3938.9     .05       0  4264.1     .12       0  4860.6     .05       0
  5004.6     .05       0  5008.6     .05       0
Bank Sta=5004.6,5008.6
XS Rating Curve= 0 ,0
Exp/Cntr=0.3,0.1

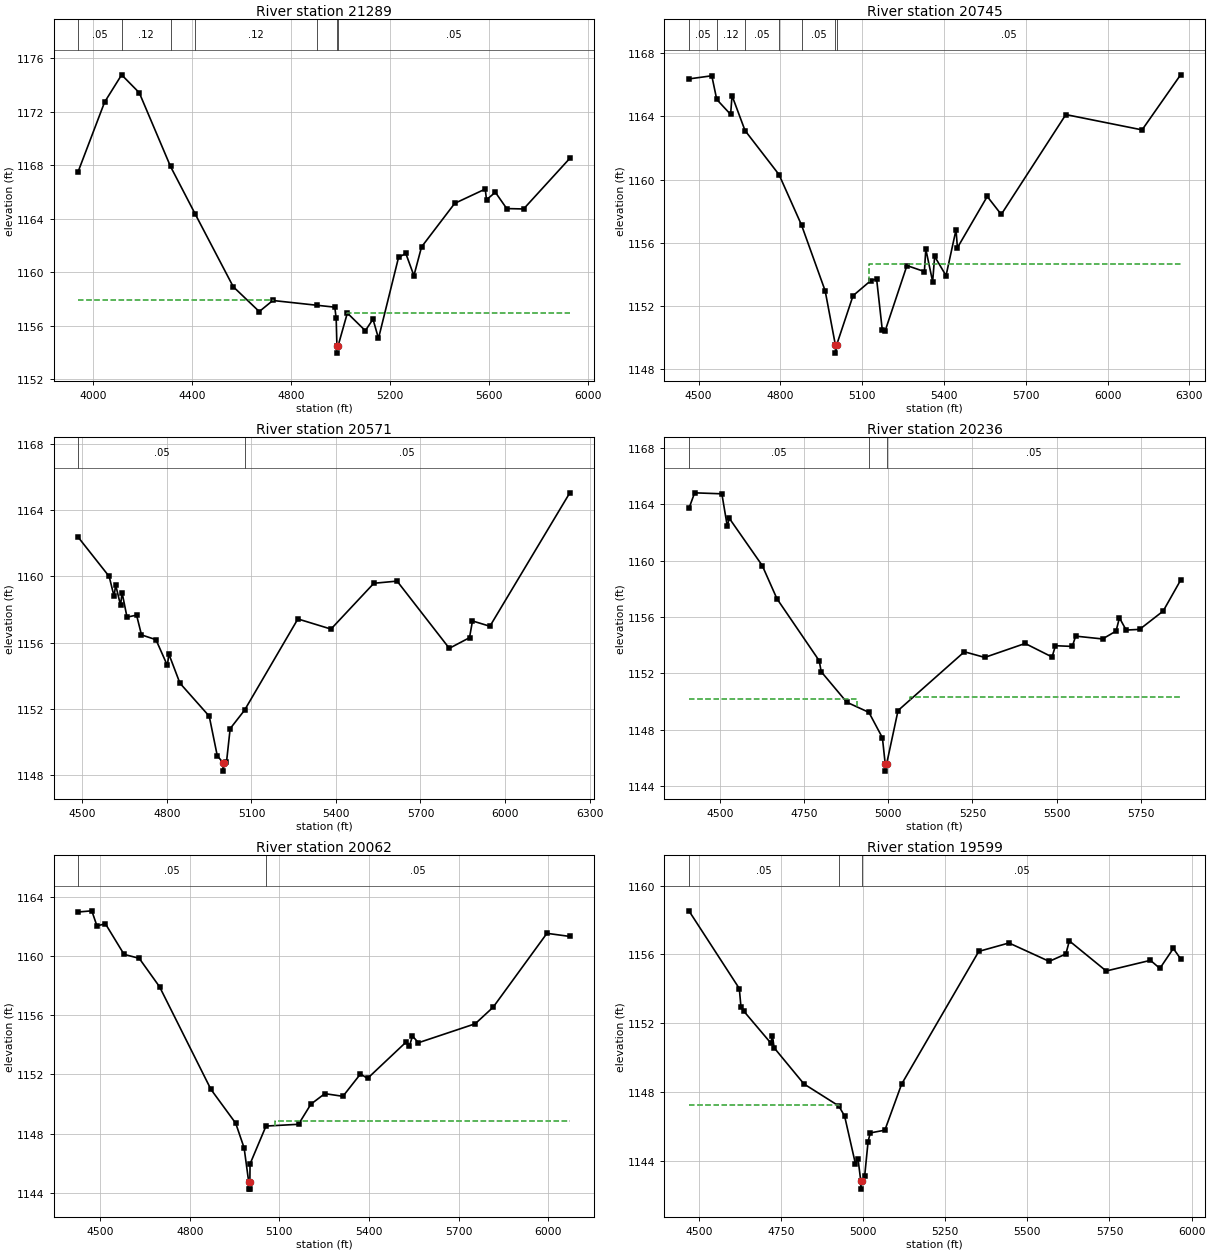
Type RM Length L Ch R = 1 ,21289   ,544,544,544
BEGIN DESCRIPTION:
Mapping XS be9cc18d
END DESCRIPTION:
XS GIS Cut Line= 5
      2797332.89     10254116.87      2796551.77     10254139.51
      2796274.43     10254116.87      2795974.45     10254037.63
      2795374.49     10253884.81
#Sta/Elev= 30
  3938.6 1167.52  4045.8 1172.73  4114.6 1174.77  4185.9 1173.43  4312.4 1167.91
  4411.4 1164.38  4566.1 1158.91  4671.4 1157.05  4726.2 1157.88  4905.7 1157.52
    4977 1157.38  4982.5 1156.54  4985.6 1154.44  4985.8 1153.94  4989.6 1154.44
  5027.7 1156.94  5100.4 1155.62  5131.5 1156.48  5153.7 1155.04  5234.9 1161.11
  5264.2  1161.4    5297 1159.74  5327.9 1161.89  5462.1 1165.15  5585.5 1166.22
  5590.7 1165.42  5626.4 1165.98  5672.4 1164.76  5740.7 1164.73  5927.7 1168.52
#Mann= 7 ,-1 , 0
  3938.6     .05       0  4114.6     .12       0  4312.4     .05       0
  4411.4     .12       0  4905.7     .05       0  4985.6     .05       0
  4989.6     .05       0
#XS Ineff= 2 , 0
         4725.85 1157.92 5026.99         1156.93
Permanent Ineff=
       F       F
Bank Sta=4985.6,4989.6
XS Rating Curve= 0 ,0
Exp/Cntr=0.3,0.1

Type RM Length L Ch R = 1 ,20745   ,174,174,174
BEGIN DESCRIPTION:
Mapping XS 885133c5
END DESCRIPTION:
XS GIS Cut Line= 6
      2797174.35     10253686.72      2796636.67     10253833.88
      2796529.13     10253879.15      2796319.71     10253947.07
      2796110.29     10253998.01      2795436.73     10253833.87
#Sta/Elev= 30
  4464.7 1166.38  4548.6 1166.58  4566.7 1165.08  4617.6 1164.13  4622.8 1165.32
  4670.4 1163.11  4795.3 1160.31  4877.6 1157.12  4964.3 1152.95    5002  1149.5
  5002.2    1149    5006  1149.5  5066.6 1152.64  5131.2 1153.59    5153  1153.7
    5174 1150.44  5184.5 1150.42  5264.2 1154.55  5328.2 1154.17  5333.4 1155.59
  5358.5 1153.53  5365.8 1155.13  5407.6 1153.91  5444.2 1156.82  5449.3 1155.68
  5558.7 1158.93  5610.1 1157.79  5846.9 1164.12  6126.5 1163.15  6267.8 1166.64
#Mann= 7 ,-1 , 0
  4464.7     .05       0  4566.7     .12       0  4670.4     .05       0
  4795.3     .12       0  4877.6     .05       0    5002     .05       0
    5006     .05       0
#XS Ineff= 2 , 0
                         5123.58         1154.64
Permanent Ineff=
       F       F
Bank Sta=5002,5006
XS Rating Curve= 0 ,0
Exp/Cntr=0.3,0.1

Type RM Length L Ch R = 1 ,20571   ,335,335,335
BEGIN DESCRIPTION:
Mapping XS 7feb242b
END DESCRIPTION:
XS GIS Cut Line= 4
      2797083.81     10253443.34      2796568.75     10253681.06
      2796246.13     10253737.66      2795420.28     10253534.02
#Sta/Elev= 30
  4484.7 1162.36  4594.9 1159.99  4612.3 1158.79  4617.9 1159.48  4635.3 1158.26
  4640.8 1159.01  4658.2 1157.54  4692.2 1157.66  4709.6 1156.47    4761 1156.18
  4801.4 1154.63  4806.9 1155.31  4846.1 1153.56  4950.1 1151.57  4978.6 1149.19
  4999.5 1148.76  4999.7 1148.26  5003.5 1148.76  5011.3 1148.79  5024.4 1150.82
  5075.4 1151.93  5264.8 1157.43  5382.3 1156.82  5534.5 1159.58  5616.9 1159.71
  5802.3 1155.66    5874  1156.3  5884.6 1157.31  5946.4 1156.99  6230.1 1165.03
#Mann= 2 ,-1 , 0
  4484.7     .05       0  5075.4     .05       0
Bank Sta=4999.5,5003.5
XS Rating Curve= 0 ,0
Exp/Cntr=0.3,0.1

Type RM Length L Ch R = 1 ,20236   ,174,174,174
BEGIN DESCRIPTION:
Mapping XS d59b18ec
END DESCRIPTION:
XS GIS Cut Line= 4
      2796970.64     10253103.72      2796466.87     10253375.42
      2796246.13      10253505.6      2795613.97     10253528.17
#Sta/Elev= 30
  4407.4  1163.7  4424.4 1164.81  4505.3 1164.74  4521.5 1162.43  4527.2 1163.01
  4625.3 1159.65  4669.1 1157.29  4794.7 1152.89  4800.4 1152.12  4876.6 1149.95
  4942.3 1149.23  4982.4 1147.43  4990.8 1145.56    4991 1145.06  4994.8 1145.56
  5028.9 1149.36    5226 1153.53  5286.5 1153.13  5406.6 1154.12  5486.6 1153.16
  5496.6 1153.96  5546.7 1153.91  5556.7 1154.64  5636.7 1154.44  5676.8    1155
  5686.8 1155.94  5706.8 1155.07  5746.8 1155.12  5816.8 1156.42  5868.6 1158.61
#Mann= 3 ,-1 , 0
  4407.4     .05       0  4942.3     .05       0  4994.8     .05       0
#XS Ineff= 2 , 0
         4905.45 1150.21 5065.45         1150.33
Permanent Ineff=
       F       F
Bank Sta=4990.8,4994.8
XS Rating Curve= 0 ,0
Exp/Cntr=0.3,0.1

Type RM Length L Ch R = 1 ,20062   ,463,463,463
BEGIN DESCRIPTION:
Mapping XS 58ccdf33
END DESCRIPTION:
XS GIS Cut Line= 4
      2796936.64     10252990.54      2796415.93     10253239.58
      2796025.39      10253335.8      2795359.12     10253352.74
#Sta/Elev= 30
  4426.3 1162.97  4472.1 1163.05  4489.3 1162.03  4517.5 1162.18    4580 1160.11
  4630.8 1159.84  4698.9 1157.92  4870.8 1150.99  4953.8  1148.7    4982 1147.03
  4997.2 1144.75  4997.4 1144.25  5000.9 1144.25  5001.2 1144.75  5001.8 1145.95
  5055.2 1148.51    5164 1148.63  5205.5 1149.99  5252.1  1150.7  5312.7 1150.52
  5371.5 1152.03  5395.1 1151.73  5525.5 1154.21  5535.5 1153.93  5545.5 1154.59
  5565.5 1154.14  5755.5 1155.42  5815.6 1156.54  5995.6 1161.53  6072.2 1161.32
#Mann= 2 ,-1 , 0
  4426.3     .05       0  5055.2     .05       0
#XS Ineff= 2 , 0
                         5086.25         1148.84
Permanent Ineff=
       F       F
Bank Sta=4997.2,5001.2
XS Rating Curve= 0 ,0
Exp/Cntr=0.3,0.1

Type RM Length L Ch R = 1 ,19599   ,599,599,599
BEGIN DESCRIPTION:
Mapping XS 42a8f4fb
END DESCRIPTION:
XS GIS Cut Line= 2
      2796749.83     10252747.17      2795283.91     10253047.15
#Sta/Elev= 30
  4470.2 1158.54  4623.5 1154.02  4628.6 1152.95  4637.8 1152.69  4719.3 1150.85
  4724.4 1151.26  4729.6 1150.57  4820.2 1148.47  4926.2 1147.19    4944  1146.6
  4976.7 1143.84  4984.8 1144.11    4993 1142.85  4993.3 1142.35    4997 1142.85
  5005.2 1143.14  5015.4 1145.11  5022.1 1145.62  5066.5 1145.78  5117.5 1148.46
  5352.3 1156.18  5444.1 1156.67  5566.6  1155.6  5617.3 1156.03  5627.9 1156.79
  5740.1 1155.04  5874.7 1155.66  5903.4 1155.19  5944.3 1156.35  5966.5 1155.75
#Mann= 3 ,-1 , 0
  4470.2     .05       0  4926.2     .05       0    4997     .05       0
#XS Ineff= 2 , 0
         4928.18 1147.27
Permanent Ineff=
       F       F
Bank Sta=4993,4997
XS Rating Curve= 0 ,0
Exp/Cntr=0.3,0.1

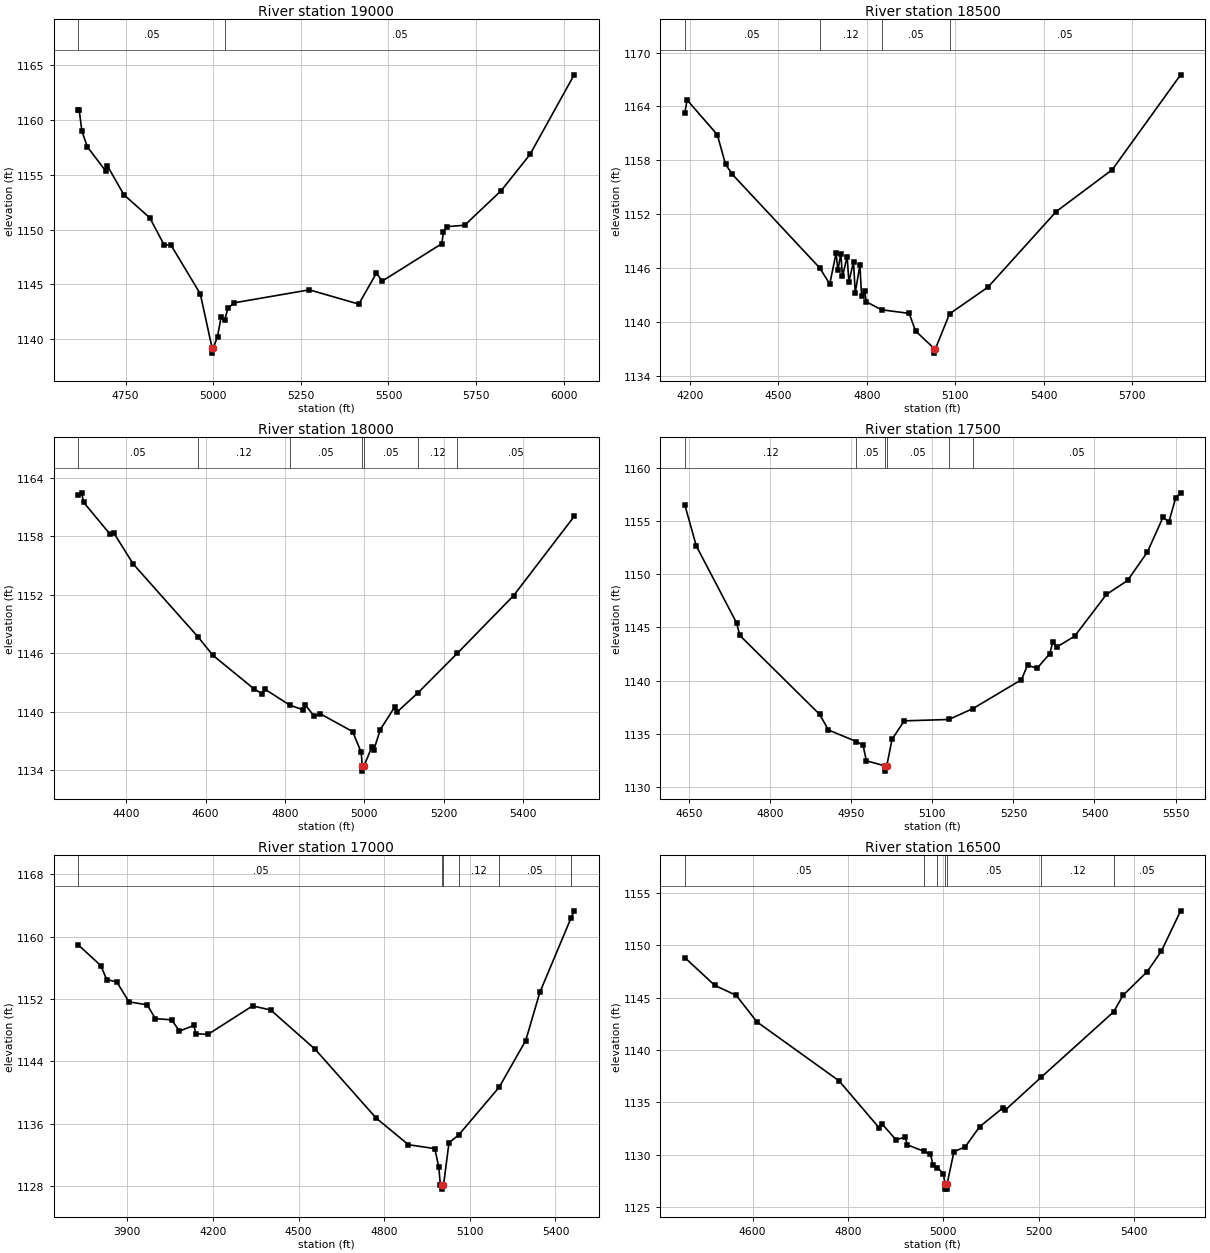
Type RM Length L Ch R = 1 ,19000   ,500,500,500
BEGIN DESCRIPTION:
SANFERNANDO030 38.0
END DESCRIPTION:
XS GIS Cut Line= 3
       2796555.7     10252253.11      2796177.92     10252325.71
      2795155.64     10252203.11
#Sta/Elev= 30
  4615.3 1160.86  4617.9 1160.86  4625.5 1158.97  4641.3 1157.53  4693.2 1155.35
  4698.3 1155.81  4745.2 1153.18    4819 1151.08  4859.7 1148.63  4880.1 1148.56
  4963.2 1144.14  4996.6 1139.24  4996.8 1138.74  5000.6 1139.24  5012.3 1140.25
  5022.4 1142.01  5032.5 1141.75  5042.5 1142.87  5060.7 1143.33  5274.2 1144.51
  5415.2 1143.21  5465.5 1146.03  5482.2 1145.31  5651.8 1148.71  5656.9 1149.77
    5667 1150.27  5717.3  1150.4  5821.4 1153.55  5903.6 1156.85  6029.6 1164.11
#Mann= 2 ,-1 , 0
  4615.3     .05       0  5032.5     .05       0
Bank Sta=4996.6,5000.6
XS Rating Curve= 0 ,0
Exp/Cntr=0.3,0.1

Type RM Length L Ch R = 1 ,18500   ,500,500,500
BEGIN DESCRIPTION:
SANFERNANDO030 37.0
END DESCRIPTION:
XS GIS Cut Line= 3
      2796655.68     10252303.11      2795946.04     10251898.07
       2795105.7     10252103.11
#Sta/Elev= 30
  4182.9  1163.3  4190.8 1164.72  4293.1 1160.86  4321.1 1157.56  4344.1 1156.44
  4640.8    1146  4674.7 1144.21  4696.3 1147.68  4702.1 1145.72  4712.1 1147.57
  4717.9 1145.08  4733.7 1147.28  4739.5 1144.47  4755.3 1146.66  4761.1 1143.22
  4776.9 1146.33  4782.7 1142.89  4792.8 1143.49  4798.5 1142.23  4850.9 1141.34
    4944 1140.94  4965.9 1138.98  5029.3 1137.01  5029.5 1136.51  5033.3 1137.01
  5081.1 1140.89  5211.3 1143.86    5443 1152.29  5633.2 1156.96    5865 1167.53
#Mann= 4 ,-1 , 0
  4182.9     .05       0  4640.8     .12       0  4850.9     .05       0
  5081.1     .05       0
Bank Sta=5029.3,5033.3
XS Rating Curve= 0 ,0
Exp/Cntr=0.3,0.1

Type RM Length L Ch R = 1 ,18000   ,500,500,500
BEGIN DESCRIPTION:
SANFERNANDO030 36.0
END DESCRIPTION:
XS GIS Cut Line= 3
      2796605.69     10252253.12      2796256.27     10251622.79
      2796355.68     10251103.12
#Sta/Elev= 30
  4279.3 1162.23  4287.3 1162.44    4293 1161.45  4359.3  1158.2  4368.6 1158.34
  4417.8 1155.14  4581.2 1147.67  4618.1 1145.81  4721.1 1142.39  4742.9 1141.84
  4748.6 1142.35    4812  1140.7  4845.9 1140.21  4851.6 1140.69  4873.9 1139.56
  4889.4  1139.8  4970.7 1137.98  4992.4 1135.85    4995 1134.43  4995.2 1133.93
    4999 1134.43  5019.2 1136.41  5024.3 1136.12  5040.4 1138.18  5076.4 1140.48
  5081.5 1139.94  5135.6 1141.96  5234.8 1146.01  5376.4 1151.91  5529.1 1160.02
#Mann= 7 ,-1 , 0
  4279.3     .05       0  4581.2     .12       0    4812     .05       0
    4995     .05       0    4999     .05       0  5135.6     .12       0
  5234.8     .05       0
Bank Sta=4995,4999
XS Rating Curve= 0 ,0
Exp/Cntr=0.3,0.1

Type RM Length L Ch R = 1 ,17500   ,500,500,500
BEGIN DESCRIPTION:
SANFERNANDO030 35.0
END DESCRIPTION:
XS GIS Cut Line= 3
      2796605.69     10252003.09      2796727.88     10251666.48
      2796505.68     10251153.11
#Sta/Elev= 30
  4641.9  1156.5  4663.2 1152.64  4737.6 1145.43  4743.7 1144.24  4891.4 1136.83
  4907.8 1135.36  4959.3 1134.28  4971.7 1133.94  4977.9 1132.47  5011.6    1132
  5011.9  1131.5  5015.6    1132  5025.5  1134.5    5048 1136.22  5130.6 1136.35
    5175 1137.37  5264.8 1140.08  5276.1 1141.45  5293.7 1141.15  5317.2 1142.52
  5322.7 1143.61  5330.6 1143.16  5363.3 1144.17  5422.1 1148.09  5461.3  1149.4
    5498 1152.08  5526.9 1155.35  5537.6 1154.88  5550.4 1157.18  5559.4 1157.63
#Mann= 6 ,-1 , 0
  4641.9     .12       0  4959.3     .05       0  5011.6     .05       0
  5015.6     .05       0  5130.6     .12       0    5175     .05       0
Bank Sta=5011.6,5015.6
XS Rating Curve= 0 ,0
Exp/Cntr=0.3,0.1

Type RM Length L Ch R = 1 ,17000   ,500,500,500
BEGIN DESCRIPTION:
SANFERNANDO030 34.0
END DESCRIPTION:
XS GIS Cut Line= 3
       2797855.7     10252153.12      2796885.72     10251331.33
      2796555.65     10251003.08
#Sta/Elev= 30
  3728.7 1158.92  3807.3 1156.28  3828.1 1154.48  3863.3 1154.18  3906.1 1151.62
  3969.8 1151.24  3998.4 1149.47  4055.6 1149.31    4083 1147.87  4133.6  1148.6
  4140.1 1147.53    4183 1147.45    4339  1151.1  4402.7 1150.57  4558.7 1145.52
  4771.8 1136.71  4884.9 1133.29  4977.2 1132.79  4991.5 1130.39  4996.7 1128.15
  5003.8 1128.09  5004.1 1127.59  5007.8 1128.09  5027.1 1133.55  5060.5 1134.52
  5202.7 1140.66  5295.8 1146.65  5345.2 1152.83    5455 1162.42  5465.5  1163.3
#Mann= 6 ,-1 , 0
  3728.7     .05       0  5003.8     .05       0  5007.8     .05       0
  5060.5     .12       0  5202.7     .05       0    5455     .12       0
Bank Sta=5003.8,5007.8
XS Rating Curve= 0 ,0
Exp/Cntr=0.3,0.1

Type RM Length L Ch R = 1 ,16500   ,500,500,500
BEGIN DESCRIPTION:
SANFERNANDO030 33.0
END DESCRIPTION:
XS GIS Cut Line= 3
      2797405.67     10251503.08      2797201.71     10251000.38
      2796705.66     10250953.11
#Sta/Elev= 30
  4457.5 1148.81  4520.4 1146.16  4565.4 1145.21  4608.9 1142.68  4781.2 1137.06
  4865.9 1132.55  4871.3 1132.96  4900.8 1131.44  4919.5 1131.68  4924.9 1130.95
  4958.7 1130.35  4973.1 1130.06  4978.5 1129.07  4987.6 1128.79    5000 1128.21
  5004.1 1127.23  5004.3 1126.73  5007.8 1126.73  5008.1 1127.23  5022.5  1130.3
  5046.2 1130.77  5076.4 1132.68  5125.4 1134.48  5130.5 1134.28  5205.8 1137.41
  5357.6 1143.63  5377.7 1145.23    5428 1147.46  5458.1 1149.44  5498.3 1153.27
#Mann= 7 ,-1 , 0
  4457.5     .05       0  4958.7     .12       0  4987.6     .05       0
  5004.1     .03       0  5008.1     .05       0  5205.8     .12       0
  5357.6     .05       0
Bank Sta=5004.1,5008.1
XS Rating Curve= 0 ,0
Exp/Cntr=0.3,0.1

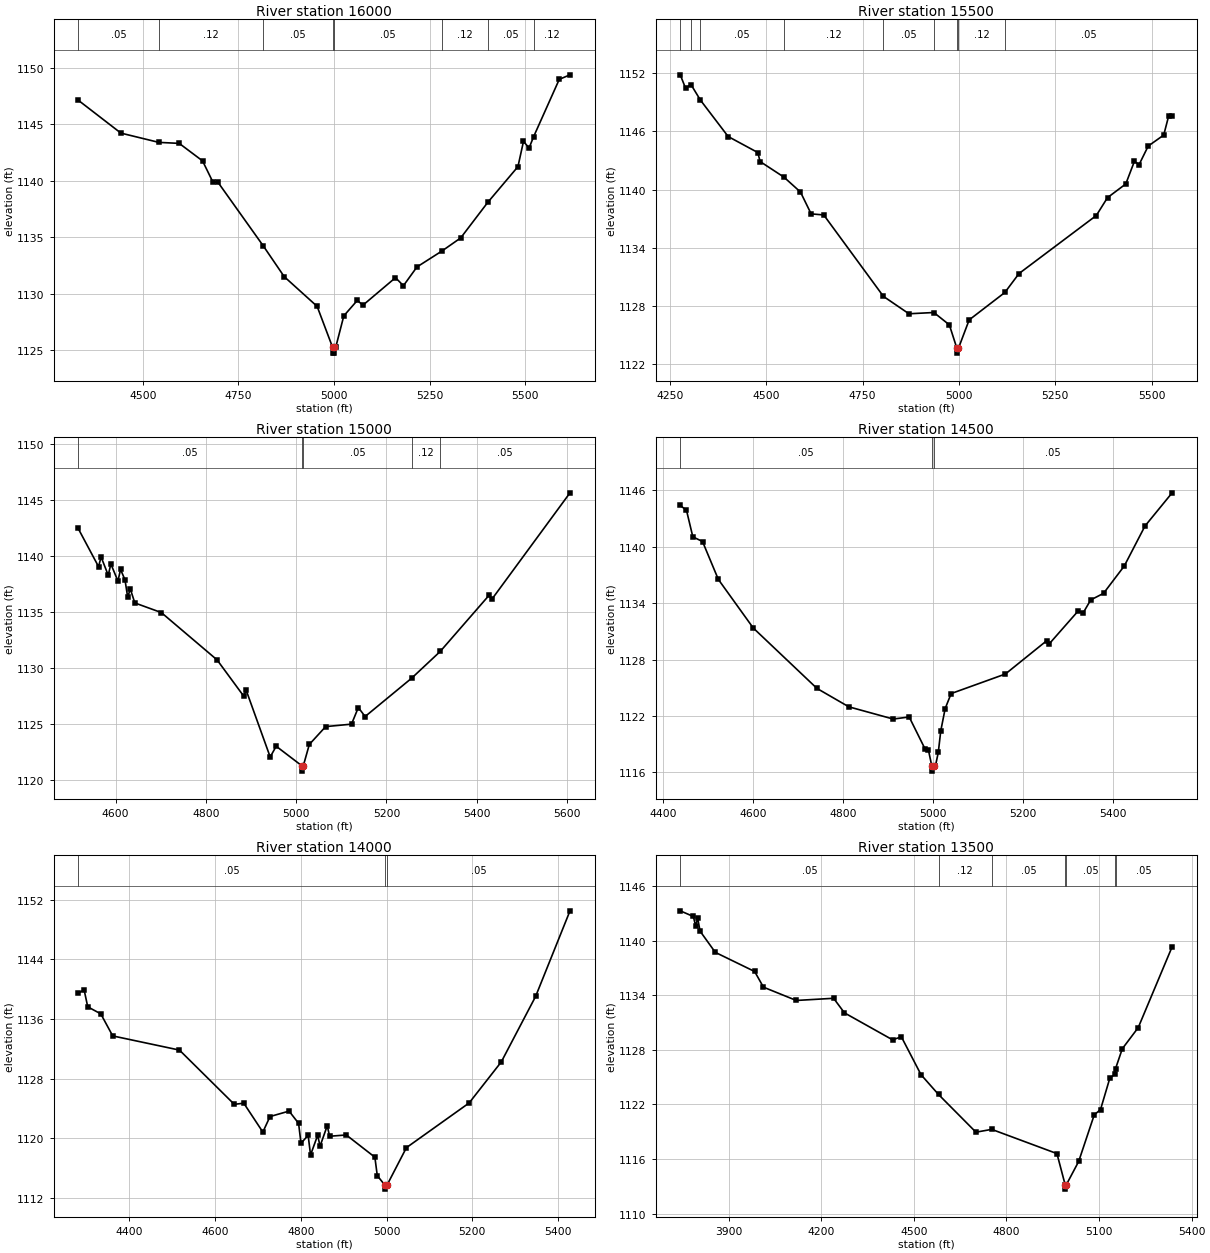
Type RM Length L Ch R = 1 ,16000   ,500,500,500
BEGIN DESCRIPTION:
SANFERNANDO030 32.0
END DESCRIPTION:
XS GIS Cut Line= 3
      2798005.65     10250403.12      2797347.68     10250526.28
      2796855.69     10250153.11
#Sta/Elev= 30
  4330.6 1147.14  4442.5 1144.22  4541.6  1143.4  4595.1 1143.31  4656.1 1141.76
  4682.7 1139.92  4696.8 1139.85  4815.5 1134.21  4869.8 1131.51  4955.9 1128.88
  4996.5 1125.24  4996.7 1124.74  5000.2 1124.74  5000.5 1125.24  5004.4 1125.24
  5025.7 1128.04  5061.1 1129.41  5075.6 1128.98  5160.9 1131.42  5181.7 1130.71
  5217.1 1132.37  5282.4 1133.78  5331.5 1134.94  5402.4 1138.09  5481.3 1141.25
  5495.8 1143.49  5510.4  1142.9  5522.4 1143.91  5589.4 1148.98  5617.5 1149.38
#Mann= 8 ,-1 , 0
  4330.6     .05       0  4541.6     .12       0  4815.5     .05       0
  4996.5     .05       0  5000.5     .05       0  5282.4     .12       0
  5402.4     .05       0  5522.4     .12       0
Bank Sta=4996.5,5000.5
XS Rating Curve= 0 ,0
Exp/Cntr=0.3,0.1

Type RM Length L Ch R = 1 ,15500   ,500,500,500
BEGIN DESCRIPTION:
SANFERNANDO030 31.0
END DESCRIPTION:
XS GIS Cut Line= 3
      2798155.67      10250403.1      2797514.91     10250068.63
      2797005.64     10249853.09
#Sta/Elev= 30
  4277.2 1151.81    4291 1150.43    4305 1150.81  4329.5 1149.21  4401.5 1145.46
  4478.5 1143.81  4484.2 1142.89  4546.2 1141.28    4589 1139.75  4616.7  1137.5
  4649.4 1137.39  4804.2 1129.01  4870.4 1127.22    4935 1127.35  4975.2 1126.08
  4994.7 1123.67  4994.9 1123.17  4998.8 1123.67  5026.6 1126.59  5119.1 1129.41
  5155.9 1131.36  5356.3 1137.33  5385.4 1139.17  5432.8 1140.58  5455.2 1142.91
  5467.3 1142.57    5491 1144.48  5531.2 1145.61  5543.8 1147.54    5553 1147.61
#Mann= 9 ,-1 , 0
  4277.2     .05       0    4305     .12       0  4329.5     .05       0
  4546.2     .12       0  4804.2     .05       0    4935     .12       0
  4994.7     .07       0  4998.8     .12       0  5119.1     .05       0
Bank Sta=4994.7,4998.8
XS Rating Curve= 0 ,0
Exp/Cntr=0.3,0.1

Type RM Length L Ch R = 1 ,15000   ,500,500,500
BEGIN DESCRIPTION:
SANFERNANDO030 30.0
END DESCRIPTION:
XS GIS Cut Line= 3
      2798155.67     10250253.08      2797913.86     10249834.74
      2797405.69     10249503.12
#Sta/Elev= 30
  4516.8 1142.46    4562 1139.05  4567.7 1139.91  4583.5 1138.28  4589.3 1139.29
    4605 1137.76  4610.8  1138.8  4620.7 1137.86  4626.6 1136.32  4632.4 1137.06
  4642.4 1135.81  4701.2 1134.95  4824.7 1130.73  4883.5 1127.51  4889.3 1128.01
  4942.4 1122.07  4955.7 1123.03  5011.8 1121.31  5012.1 1120.81    5016 1121.31
  5029.1 1123.19  5065.3 1124.78  5122.6    1125  5137.7 1126.48  5152.8 1125.68
  5255.9  1129.1  5319.1 1131.48  5427.4 1136.49  5433.3 1136.12  5606.8 1145.63
#Mann= 5 ,-1 , 0
  4516.8     .05       0  5011.8     .03       0    5016     .05       0
  5255.9     .12       0  5319.1     .05       0
Bank Sta=5011.8,5016
XS Rating Curve= 0 ,0
Exp/Cntr=0.3,0.1

Type RM Length L Ch R = 1 ,14500   ,500,500,500
BEGIN DESCRIPTION:
SANFERNANDO030 29.0
END DESCRIPTION:
XS GIS Cut Line= 3
      2798455.68     10249803.11      2798040.42     10249423.54
      2797555.68     10249203.11
#Sta/Elev= 30
  4437.4  1144.4  4451.3 1143.88  4465.4 1141.06    4487 1140.56  4522.2 1136.53
    4600 1131.36  4741.7 1124.94  4812.7 1122.98  4911.6 1121.68  4947.1  1121.9
  4982.2 1118.52  4989.7 1118.43  4997.7 1116.64    4998 1116.14  5001.9 1116.64
  5005.3 1116.64  5011.9 1118.13  5017.4 1120.42  5027.2 1122.79  5040.5 1124.39
  5161.3 1126.47  5253.5 1130.02    5259 1129.68  5322.7 1133.14  5334.8    1133
  5351.3 1134.35  5379.8 1135.05    5426 1137.96  5472.1 1142.21  5532.5 1145.74
#Mann= 3 ,-1 , 0
  4437.4     .05       0  4997.7     .05       0  5001.9     .05       0
Bank Sta=4997.7,5001.9
XS Rating Curve= 0 ,0
Exp/Cntr=0.3,0.1

Type RM Length L Ch R = 1 ,14000   ,500,500,500
BEGIN DESCRIPTION:
SANFERNANDO030 28.0
END DESCRIPTION:
XS GIS Cut Line= 3
      2798505.68      10249653.1      2798179.37     10249011.52
      2797805.66      10248803.1
#Sta/Elev= 30
  4280.2 1139.44  4294.1 1139.93  4302.6 1137.64    4333  1136.7  4360.9 1133.74
  4516.6 1131.84  4644.5 1124.57  4666.7 1124.72  4711.2 1120.85  4727.9 1122.93
  4772.4 1123.66  4794.6 1122.02  4800.2 1119.35  4816.9 1120.41  4822.5 1117.78
  4839.1 1120.42  4844.7 1118.96  4861.4 1121.69    4867 1120.29  4905.9 1120.46
  4972.6 1117.48  4978.2 1115.01  4996.4  1113.7  4996.7  1113.2  5000.6  1113.7
  5046.2 1118.76  5192.5 1124.75  5267.6 1130.26  5347.7 1139.04  5427.9 1150.51
#Mann= 3 ,-1 , 0
  4280.2     .05       0  4996.4     .05       0  5000.6     .05       0
Bank Sta=4996.4,5000.6
XS Rating Curve= 0 ,0
Exp/Cntr=0.3,0.1

Type RM Length L Ch R = 1 ,13500   ,500,500,500
BEGIN DESCRIPTION:
SANFERNANDO030 27.0
END DESCRIPTION:
XS GIS Cut Line= 3
      2799155.68     10249503.11      2798339.43     10248547.58
      2798005.68     10248503.11
#Sta/Elev= 30
  3743.3 1143.26  3785.6 1142.64  3793.3 1141.61  3799.8 1142.45  3807.5 1141.03
  3856.9  1138.7  3984.3  1136.6  4012.8 1134.88  4119.3 1133.42  4240.1 1133.66
  4275.2 1132.06  4431.1  1129.1  4459.6 1129.43  4523.3 1125.27  4579.9  1123.1
  4701.2 1118.96  4752.3 1119.27  4963.6 1116.61    4990 1113.21  4990.3 1112.71
  4994.3 1113.21    5034 1115.75  5084.5 1120.87  5104.7 1121.44  5134.9 1124.89
  5150.5  1125.3  5153.4 1125.93  5175.3 1128.12  5226.9 1130.44  5336.7 1139.31
#Mann= 7 ,-1 , 0
  3743.3     .05       0  4579.9     .12       0  4752.3     .05       0
    4990     .05       0  4994.3     .05       0  5150.5     .12       0
  5153.4     .05       0
Bank Sta=4990,4994.3
XS Rating Curve= 0 ,0
Exp/Cntr=0.3,0.1

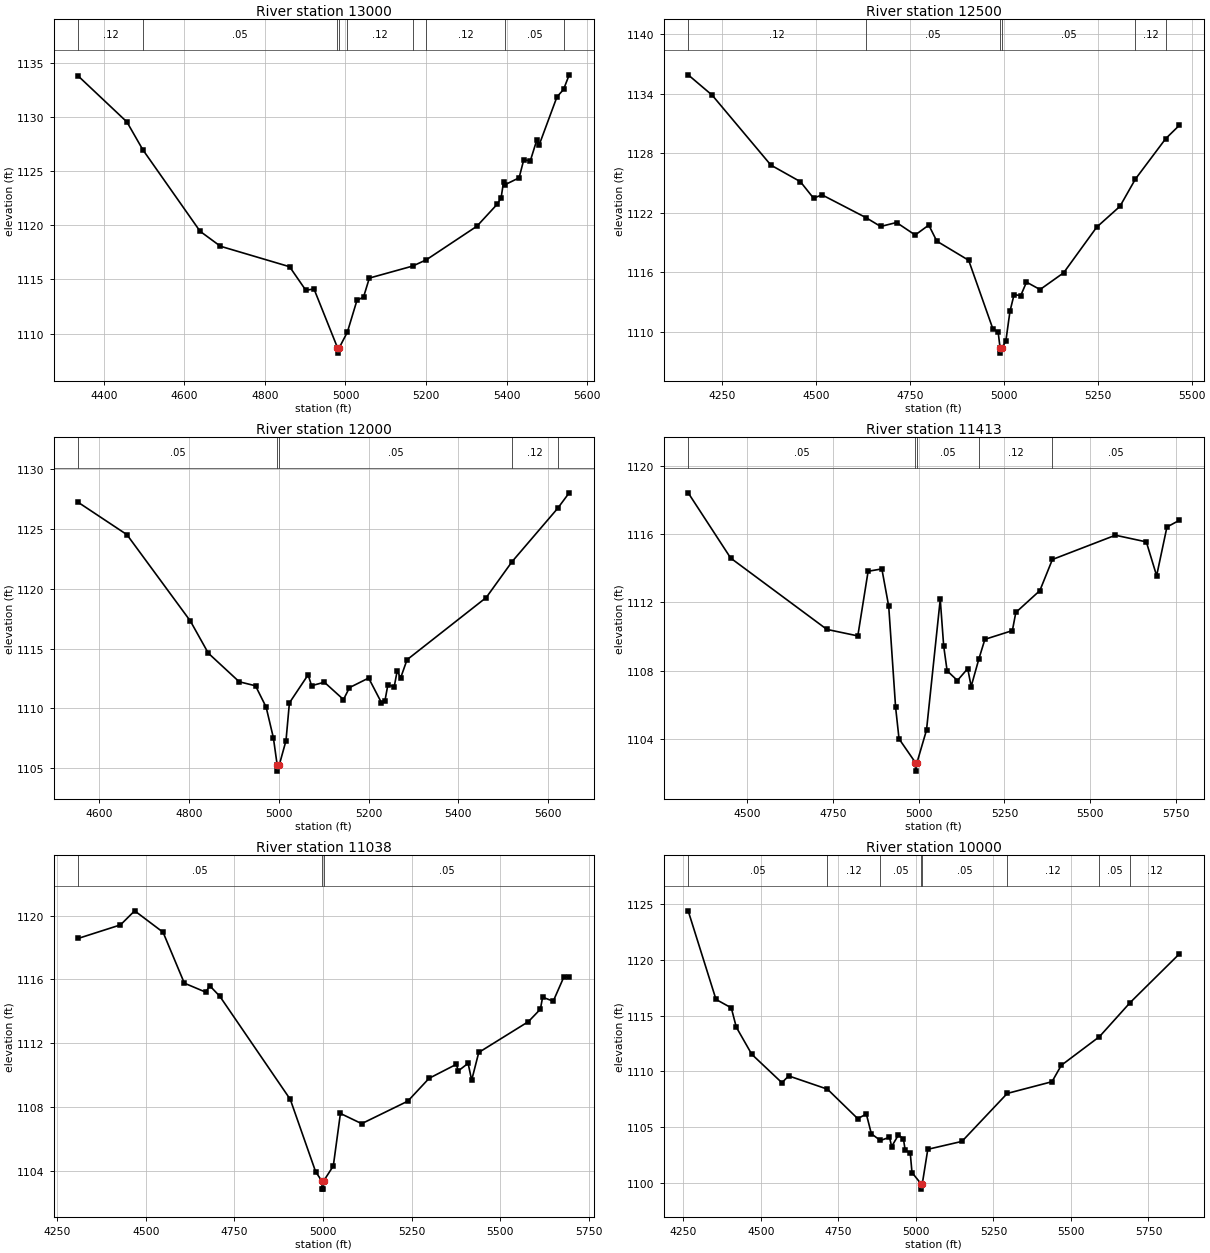
Type RM Length L Ch R = 1 ,13000   ,500,500,500
BEGIN DESCRIPTION:
SANFERNANDO030 26.0
END DESCRIPTION:
XS GIS Cut Line= 3
      2799205.69     10248053.11      2798548.24     10248146.15
      2798055.64     10248403.13
#Sta/Elev= 30
    4336  1133.8  4457.2 1129.55  4496.6 1126.99    4639 1119.45  4689.5 1118.07
  4861.2 1116.18  4901.6    1114  4921.8 1114.13  4980.2  1108.7  4980.5  1108.2
  4984.6  1108.7  5004.7 1110.14  5028.5 1113.07  5044.9 1113.38  5059.3 1115.13
  5166.9 1116.24  5200.9 1116.82  5326.4 1119.92  5376.3 1121.93  5386.4 1122.52
  5392.7 1124.04  5397.2 1123.77  5431.2 1124.39  5442.8 1126.06    5459 1125.95
  5475.4 1127.91  5481.1 1127.43  5525.2 1131.86  5541.6 1132.55  5555.6  1133.9
#Mann= 9 ,-1 , 0
    4336     .12       0  4496.6     .05       0  4980.2     .05       0
  4984.6     .05       0  5004.7     .12       0  5166.9     .05       0
  5200.9     .12       0  5397.2     .05       0  5541.6     .12       0
Bank Sta=4980.2,4984.6
XS Rating Curve= 0 ,0
Exp/Cntr=0.3,0.1

Type RM Length L Ch R = 1 ,12500   ,500,500,500
BEGIN DESCRIPTION:
SANFERNANDO030 25.0
END DESCRIPTION:
XS GIS Cut Line= 3
      2798805.71     10247403.09      2798149.83     10247928.22
       2797955.7     10248353.07
#Sta/Elev= 30
  4159.8 1135.91  4223.9 1133.85  4379.9 1126.81  4458.4 1125.14  4493.6 1123.47
    4516 1123.81  4632.7 1121.52  4672.2 1120.62  4714.5 1121.02  4764.1 1119.76
  4800.3 1120.76  4821.7 1119.14  4906.5 1117.21  4970.6 1110.33    4985 1109.96
  4990.2 1108.35  4990.6 1107.85  4994.7 1108.35  5005.4 1109.05  5016.4 1112.06
  5027.4 1113.76    5045 1113.64  5060.4 1115.01  5096.5 1114.26  5159.3 1115.95
  5247.3 1120.55  5309.2 1122.65  5350.5 1125.41  5430.9 1129.47  5467.1 1130.81
#Mann= 6 ,-1 , 0
  4159.8     .12       0  4632.7     .05       0  4990.2     .05       0
  4994.7     .05       0  5350.5     .12       0  5430.9     .05       0
Bank Sta=4990.2,4994.7
XS Rating Curve= 0 ,0
Exp/Cntr=0.3,0.1

Type RM Length L Ch R = 1 ,12000   ,587,587,587
BEGIN DESCRIPTION:
SANFERNANDO030 24.0
END DESCRIPTION:
XS GIS Cut Line= 3
      2798305.72      10247353.1      2797894.45     10247529.25
      2797405.65     10247953.14
#Sta/Elev= 30
  4552.6 1127.24  4661.4 1124.53  4802.8  1117.3  4842.8 1114.61  4911.6 1112.22
    4948 1111.88  4971.6  1110.1  4987.8 1107.53  4996.3 1105.24  4996.6 1104.74
  5000.8 1105.24  5015.9 1107.29  5023.5 1110.45  5065.2  1112.8  5072.9 1111.89
  5101.4 1112.18    5144 1110.73  5157.4 1111.73  5200.1 1112.53  5228.6 1110.47
  5236.2 1110.59  5242.9 1111.95  5257.1 1111.81  5263.7 1113.13  5271.4 1112.54
  5285.6 1114.06  5462.2 1119.27  5519.7 1122.27  5621.3 1126.73    5647 1128.03
#Mann= 5 ,-1 , 0
  4552.6     .05       0  4996.3     .05       0  5000.8     .05       0
  5519.7     .12       0  5621.3     .05       0
Bank Sta=4996.3,5000.8
XS Rating Curve= 0 ,0
Exp/Cntr=0.3,0.1

Type RM Length L Ch R = 1 ,11413   ,375,375,375
BEGIN DESCRIPTION:
Mapping XS 006c9d02
END DESCRIPTION:
XS GIS Cut Line= 2
      2798099.62     10247331.46      2796669.82     10247331.46
#Sta/Elev= 30
  4329.1 1118.41    4453 1114.59    4733 1110.42    4823 1110.04    4853 1113.82
    4893 1113.96    4913 1111.77    4933 1105.87    4943 1104.02  4990.7 1102.63
    4991 1102.13  4995.3 1102.63    5023 1104.53    5063 1112.18    5073 1109.45
    5083    1108    5113 1107.43    5143 1108.13    5153 1107.08    5175 1108.66
    5193 1109.84    5273 1110.35    5283 1111.41    5353 1112.69  5389.5 1114.51
    5573 1115.93    5663 1115.54    5693 1113.56    5723 1116.41  5758.9  1116.8
#Mann= 5 ,-1 , 0
  4329.1     .05       0  4990.7     .03       0  4995.3     .05       0
    5175     .12       0  5389.5     .05       0
Bank Sta=4990.7,4995.3
XS Rating Curve= 0 ,0
Exp/Cntr=0.3,0.1

Type RM Length L Ch R = 1 ,11038   ,1038,1038,1038
BEGIN DESCRIPTION:
Mapping XS f41adba5
END DESCRIPTION:
XS GIS Cut Line= 2
      2797895.17      10247113.9      2796510.74     10247054.57
#Sta/Elev= 30
    4309 1118.57  4428.6 1119.42  4468.6  1120.3  4548.7 1118.96  4608.8 1115.77
  4668.8 1115.21  4680.8  1115.6  4708.8 1114.95  4907.7 1108.49  4979.1 1103.97
  4996.8 1103.37  4997.1 1102.87  5001.1 1102.87  5001.5 1103.37  5029.1 1104.32
  5049.2 1107.61  5109.2 1106.97  5239.3 1108.38  5299.4 1109.81  5376.5 1110.69
  5381.5 1110.27  5409.5 1110.75  5419.5 1109.69  5439.5 1111.43  5579.6 1113.36
  5613.4 1114.14  5619.7 1114.89  5649.7 1114.64  5679.7 1116.16  5694.7 1116.14
#Mann= 3 ,-1 , 0
    4309     .05       0  4996.8     .03       0  5001.5     .05       0
Bank Sta=4996.8,5001.5
XS Rating Curve= 0 ,0
Exp/Cntr=0.3,0.1

Type RM Length L Ch R = 1 ,10000   ,1000,1000,1000
BEGIN DESCRIPTION:
SANFERNANDO030 20.0
END DESCRIPTION:
XS GIS Cut Line= 3
      2797655.69     10246753.12      2797303.83     10246108.15
      2796455.72     10246153.11
#Sta/Elev= 30
  4265.3  1124.4    4355 1116.46  4404.4  1115.7  4420.5 1113.97  4470.4 1111.54
  4567.6 1108.99  4589.5  1109.6  4714.6 1108.41  4812.1 1105.77    4840 1106.18
  4856.2 1104.41  4885.4 1103.81  4914.6  1104.1  4921.7 1103.27  4943.5 1104.31
  4959.6 1103.96  4965.3 1102.92  4981.5 1102.72  4987.2 1100.94  5015.7 1099.95
  5016.1 1099.45  5020.6 1099.95  5038.2 1103.02  5148.4 1103.73  5294.5 1108.03
  5438.8 1109.08  5468.8 1110.55  5591.9 1113.12    5691 1116.18  5849.3 1120.53
#Mann= 8 ,-1 , 0
  4265.3     .05       0  4714.6     .12       0  4885.4     .05       0
  5015.7     .05       0  5020.6     .05       0  5294.5     .12       0
  5591.9     .05       0    5691     .12       0
Bank Sta=5015.7,5020.6
XS Rating Curve= 0 ,0
Exp/Cntr=0.3,0.1