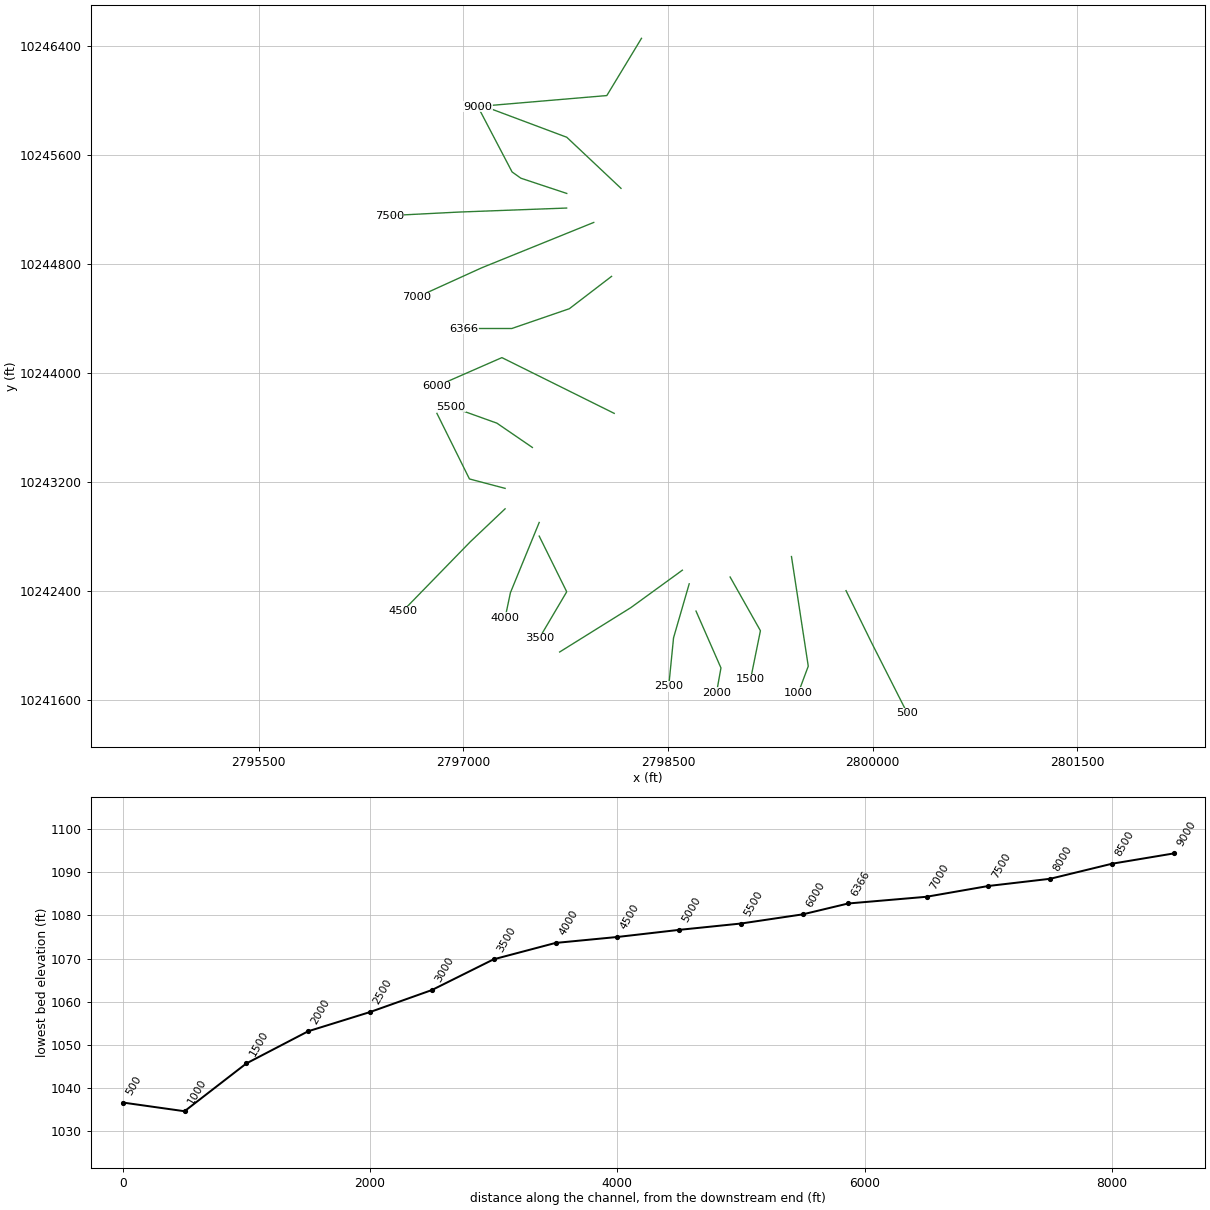
HEC-RAS study SANFERNANDO030.prj: SANFERNANDO030 Base Level Engineering

--- SANFERNANDO030.g01 (geometry) --- (continued)

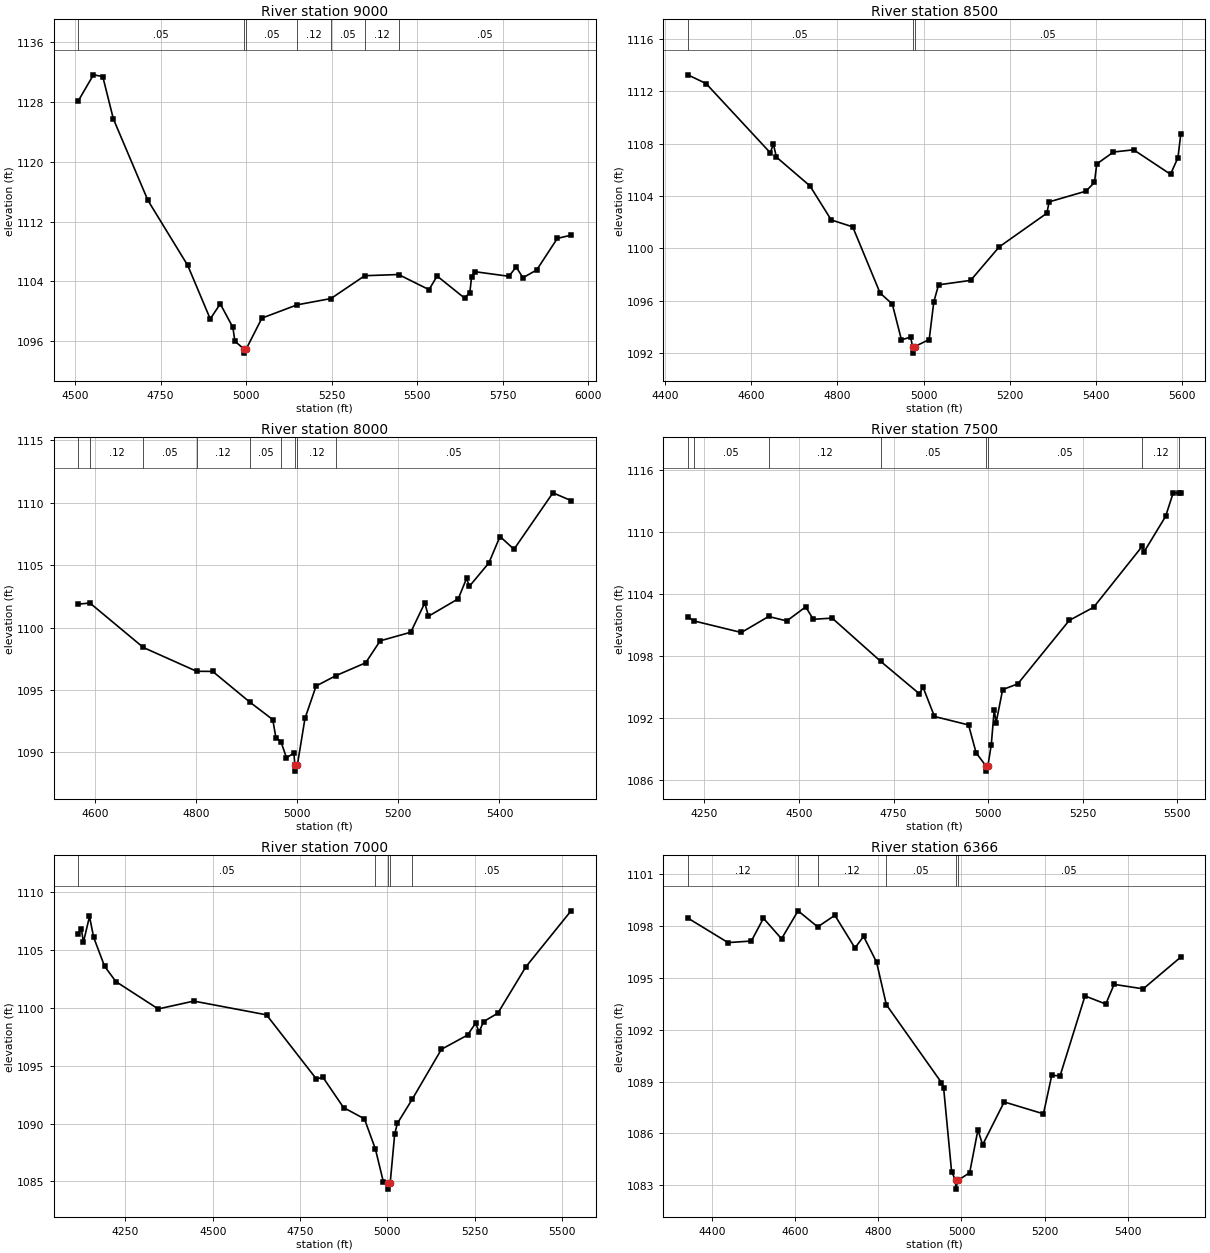
Type RM Length L Ch R = 1 ,9000    ,500,500,500
BEGIN DESCRIPTION:
SANFERNANDO030 18.0
END DESCRIPTION:
XS GIS Cut Line= 3
       2798305.7     10246453.14      2798051.58     10246033.48
      2797105.69     10245953.11
#Sta/Elev= 30
  4509.4 1128.15    4554 1131.66  4581.2 1131.43  4612.2 1125.75  4713.1 1114.84
  4829.5 1106.12  4895.2 1098.96  4924.5 1100.98  4961.3 1097.83  4967.2 1095.98
  4994.8 1094.88  4995.2 1094.38  4999.7 1094.88  5046.1 1099.07    5149 1100.85
  5247.8 1101.69  5346.5 1104.75  5445.3 1104.91  5534.4 1102.88  5557.9 1104.71
  5638.2 1101.75  5653.6  1102.5  5658.6 1104.59  5668.3 1105.29  5767.9 1104.67
  5788.7 1105.92  5808.8 1104.48  5848.9 1105.52  5909.2 1109.75  5949.3 1110.18
#Mann= 7 ,-1 , 0
  4509.4     .05       0  4994.8     .05       0  4999.7     .05       0
    5149     .12       0  5247.8     .05       0  5346.5     .12       0
  5445.3     .05       0
Bank Sta=4994.8,4999.7
XS Rating Curve= 0 ,0
Exp/Cntr=0.3,0.1

Type RM Length L Ch R = 1 ,8500    ,500,500,500
BEGIN DESCRIPTION:
SANFERNANDO030 17.0
END DESCRIPTION:
XS GIS Cut Line= 3
      2798155.66     10245353.13      2797757.88     10245727.73
      2797199.59     10245936.91
#Sta/Elev= 30
  4453.6 1113.26  4495.8 1112.59  4644.7  1107.3  4651.6 1107.98  4658.9 1106.97
  4736.6 1104.77  4785.9 1102.17  4835.7 1101.64  4899.2 1096.58  4927.5 1095.74
  4948.6 1093.01    4970 1093.21  4974.4 1092.49  4974.8 1091.99  4979.4 1092.49
    5013 1093.03  5023.7 1095.91  5034.7 1097.21  5109.1 1097.55  5175.3 1100.11
  5285.7 1102.68  5291.1 1103.55  5376.5 1104.37  5396.1 1105.04  5401.5 1106.45
  5440.2 1107.36  5486.9 1107.53  5572.4 1105.66  5589.7 1106.93  5596.2 1108.74
#Mann= 3 ,-1 , 0
  4453.6     .05       0  4974.4     .05       0  4979.4     .05       0
Bank Sta=4974.4,4979.4
XS Rating Curve= 0 ,0
Exp/Cntr=0.3,0.1

Type RM Length L Ch R = 1 ,8000    ,500,500,500
BEGIN DESCRIPTION:
SANFERNANDO030 16.0
END DESCRIPTION:
XS GIS Cut Line= 4
       2797757.8     10245315.77      2797421.42     10245427.45
      2797356.96     10245473.22      2797105.68     10245953.12
#Sta/Elev= 30
  4566.5 1101.88  4589.7 1101.97  4695.3 1098.41  4800.8  1096.5  4832.6 1096.49
  4906.4 1094.02  4951.5 1092.63  4957.6 1091.19  4967.7 1090.86  4978.5 1089.58
  4993.3 1089.93  4995.2    1089  4995.6  1088.5  5000.2    1089  5015.2 1092.72
  5037.2 1095.32  5076.4 1096.15  5135.3 1097.18    5164 1098.94  5224.5 1099.63
  5252.3 1101.98  5259.5 1100.91  5318.5 1102.31  5334.9 1103.94  5340.5 1103.31
    5379 1105.18  5401.1  1107.3  5428.8 1106.28  5505.8  1110.8  5541.7 1110.18
#Mann= 9 ,-1 , 0
  4566.5     .05       0  4589.7     .12       0  4695.3     .05       0
  4800.8     .12       0  4906.4     .05       0  4967.7     .12       0
  4995.2     .07       0  5000.2     .12       0  5076.4     .05       0
Bank Sta=4995.2,5000.2
XS Rating Curve= 0 ,0
Exp/Cntr=0.3,0.1

Type RM Length L Ch R = 1 ,7500    ,500,500,500
BEGIN DESCRIPTION:
SANFERNANDO030 15.0
END DESCRIPTION:
XS GIS Cut Line= 3
      2797756.76     10245208.66      2796963.91     10245179.07
      2796455.67     10245153.11
#Sta/Elev= 30
  4206.6 1101.76  4222.6 1101.37  4347.8 1100.25  4419.9  1101.8  4467.9 1101.37
  4517.9 1102.73  4537.9 1101.53  4587.9 1101.64  4715.9 1097.46  4818.1 1094.32
  4828.1 1094.94  4858.1 1092.12  4948.2  1091.3  4968.2  1088.6  4994.1 1087.33
  4994.5 1086.83  4999.2 1087.33  5008.2 1089.38    5016 1092.77    5021 1091.53
  5038.3 1094.72  5078.3 1095.28  5214.2 1101.42  5278.6 1102.69  5406.7 1108.58
  5412.3 1108.08  5468.8 1111.49  5488.9 1113.77  5505.3 1113.74  5508.9 1113.74
#Mann= 8 ,-1 , 0
  4206.6     .12       0  4222.6     .05       0  4419.9     .12       0
  4715.9     .05       0  4994.1     .05       0  4999.2     .05       0
  5406.7     .12       0  5505.3     .05       0
Bank Sta=4994.1,4999.2
XS Rating Curve= 0 ,0
Exp/Cntr=0.3,0.1

Type RM Length L Ch R = 1 ,7000    ,634,634,634
BEGIN DESCRIPTION:
SANFERNANDO030 14.0
END DESCRIPTION:
XS GIS Cut Line= 3
      2797955.69     10245103.11      2797135.11     10244770.84
      2796655.73     10244553.13
#Sta/Elev= 30
  4114.7 1106.44  4124.1 1106.81  4129.5 1105.67  4147.1 1107.92    4159 1106.12
  4190.2 1103.62  4222.6 1102.29  4343.9 1099.92  4445.8  1100.6  4654.1 1099.41
    4797 1093.86  4815.7 1094.01  4874.7 1091.39  4934.6 1090.41    4966  1087.8
  4988.6 1084.99  5003.2 1084.83  5003.5 1084.33  5008.3 1084.83  5021.3 1089.09
  5028.8 1090.01  5071.4  1092.1  5155.2 1096.43    5230 1097.66    5253 1098.69
    5263 1097.94    5276 1098.83  5316.7 1099.55  5396.9 1103.56  5526.5 1108.41
#Mann= 5 ,-1 , 0
  4114.7     .05       0    4966     .12       0  5003.2     .07       0
  5008.3     .12       0  5071.4     .05       0
Bank Sta=5003.2,5008.3
XS Rating Curve= 0 ,0
Exp/Cntr=0.3,0.1

Type RM Length L Ch R = 1 ,6366    ,366,366,366
BEGIN DESCRIPTION:
Mapping XS 8e04acca
END DESCRIPTION:
XS GIS Cut Line= 4
      2798086.36      10244707.6      2797776.54     10244470.29
      2797354.62     10244325.25      2797005.24     10244325.25
#Sta/Elev= 30
  4341.8 1098.47  4438.4 1097.05  4494.5 1097.14  4523.6 1098.46  4567.1 1097.27
  4606.9 1098.89  4654.1 1097.96  4695.4 1098.63  4743.8 1096.74  4764.5 1097.41
  4795.7 1095.92  4819.3 1093.45  4951.9 1088.94  4957.2  1088.6  4976.2 1083.79
  4985.9 1083.27  4986.3 1082.77  4991.1 1083.27  5019.7 1083.72  5039.6  1086.2
  5050.9 1085.34  5102.8 1087.82  5197.2 1087.13  5217.2 1089.36  5237.2 1089.33
  5297.2 1093.96  5347.2 1093.49  5367.2 1094.63  5437.2 1094.37  5527.6 1096.21
#Mann= 6 ,-1 , 0
  4341.8     .12       0  4606.9     .05       0  4654.1     .12       0
  4819.3     .05       0  4985.9     .05       0  4991.1     .05       0
Bank Sta=4985.9,4991.1
XS Rating Curve= 0 ,0
Exp/Cntr=0.3,0.1

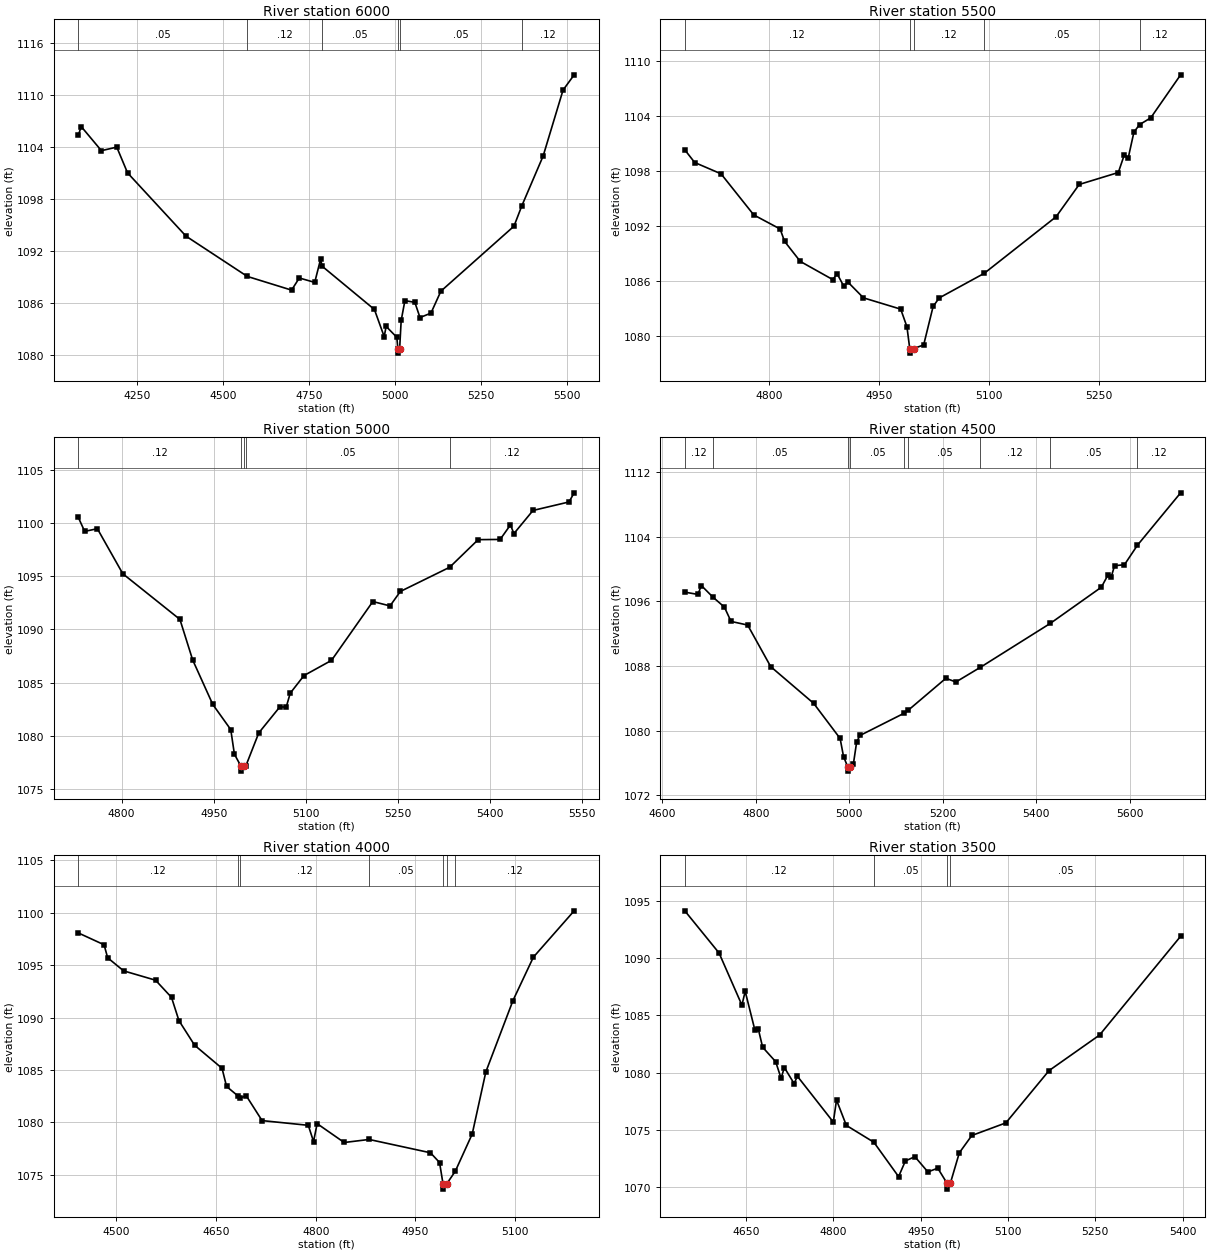
Type RM Length L Ch R = 1 ,6000    ,500,500,500
BEGIN DESCRIPTION:
SANFERNANDO030 12.0
END DESCRIPTION:
XS GIS Cut Line= 3
      2798105.66     10243703.12       2797282.2     10244111.82
       2796805.7     10243903.12
#Sta/Elev= 30
  4080.7 1105.37  4089.1 1106.37  4147.7 1103.59  4192.3    1104  4223.6 1101.03
  4393.3 1093.74  4571.2  1089.1  4699.8 1087.52  4722.2 1088.92    4767 1088.41
  4783.8 1091.05    4789 1090.26  4940.3 1085.29  4968.7 1082.16  4974.3 1083.34
  5005.4 1082.08  5008.3 1080.76  5008.7 1080.26  5013.5 1080.76    5018 1084.02
  5028.8 1086.31  5057.7 1086.11  5072.6 1084.36  5104.4 1084.87  5133.3  1087.4
  5345.5 1094.89  5368.1 1097.22  5430.2 1102.98  5487.9 1110.57  5520.2 1112.33
#Mann= 6 ,-1 , 0
  4080.7     .05       0  4571.2     .12       0    4789     .05       0
  5008.3     .05       0  5013.5     .05       0  5368.1     .12       0
Bank Sta=5008.3,5013.5
XS Rating Curve= 0 ,0
Exp/Cntr=0.3,0.1

Type RM Length L Ch R = 1 ,5500    ,500,500,500
BEGIN DESCRIPTION:
SANFERNANDO030 11.0
END DESCRIPTION:
XS GIS Cut Line= 3
      2797505.68     10243453.11      2797245.44     10243631.29
      2796905.71      10243753.1
#Sta/Elev= 30
  4684.6 1100.27  4698.1 1098.89    4734 1097.66  4778.7 1093.18  4814.6 1091.65
  4820.7  1090.3  4842.1 1088.12  4886.4 1086.14  4892.4 1086.77  4901.3 1085.44
  4907.3 1085.85  4928.3 1084.15  4979.1 1082.92  4987.6    1081  4991.4 1078.63
  4991.8 1078.13  4996.7 1078.63  5010.4 1079.02  5023.3 1083.21  5031.6 1084.14
    5093 1086.82    5191 1092.98  5222.6  1096.5  5275.9  1097.8  5284.1 1099.73
  5289.4 1099.38  5297.2  1102.2  5304.9 1103.02  5320.1 1103.75  5360.9 1108.44
#Mann= 5 ,-1 , 0
  4684.6     .12       0  4991.4     .07       0  4996.7     .12       0
    5093     .05       0  5304.9     .12       0
Bank Sta=4991.4,4996.7
XS Rating Curve= 0 ,0
Exp/Cntr=0.3,0.1

Type RM Length L Ch R = 1 ,5000    ,500,500,500
BEGIN DESCRIPTION:
SANFERNANDO030 10.0
END DESCRIPTION:
XS GIS Cut Line= 3
      2797305.65     10243153.12      2797044.19      10243222.1
      2796805.68     10243703.12
#Sta/Elev= 30
  4729.6 1100.55  4739.9 1099.24  4760.6 1099.49    4802 1095.25    4895 1090.95
  4915.7 1087.14  4948.5 1082.94  4977.8 1080.57  4983.7 1078.26    4994 1077.16
  4994.4 1076.66  4999.3 1077.16  5002.4 1077.16  5023.4 1080.26  5057.7 1082.71
  5068.1 1082.69  5074.6    1084    5097 1085.66  5141.8 1087.09  5209.1 1092.63
  5237.1 1092.22  5253.9 1093.58  5334.2 1095.86  5380.6 1098.46  5416.4 1098.48
  5433.2 1099.85  5438.8 1099.03  5469.9 1101.21  5528.5 1102.01  5536.9 1102.87
#Mann= 5 ,-1 , 0
  4729.6     .12       0    4994     .07       0  4999.3     .12       0
  5002.4     .05       0  5334.2     .12       0
Bank Sta=4994,4999.3
XS Rating Curve= 0 ,0
Exp/Cntr=0.3,0.1

Type RM Length L Ch R = 1 ,4500    ,500,500,500
BEGIN DESCRIPTION:
SANFERNANDO030 9.0
END DESCRIPTION:
XS GIS Cut Line= 3
      2797305.66     10243003.09      2797050.26     10242761.16
       2796555.7     10242253.13
#Sta/Elev= 30
  4648.2 1097.14  4676.3 1096.86  4683.6 1097.96  4707.9 1096.55  4732.9 1095.29
  4747.1 1093.52  4782.7 1093.07    4832 1087.93  4923.9 1083.39  4980.5 1079.05
  4987.8 1076.81    4997 1075.51  4997.4 1075.01  5002.4 1075.51    5009 1075.94
    5016 1078.65  5023.1 1079.42  5117.8 1082.18  5126.7 1082.56  5206.8 1086.49
  5228.2 1086.03  5280.7 1087.85    5430 1093.27  5539.4 1097.75  5553.5 1099.25
  5560.5 1099.03  5567.7 1100.41  5588.8 1100.53  5616.7 1102.95    5709 1109.42
#Mann= 9 ,-1 , 0
  4648.2     .12       0  4707.9     .05       0    4997     .05       0
  5002.4     .05       0  5117.8     .12       0  5126.7     .05       0
  5280.7     .12       0    5430     .05       0  5616.7     .12       0
Bank Sta=4997,5002.4
XS Rating Curve= 0 ,0
Exp/Cntr=0.3,0.1

Type RM Length L Ch R = 1 ,4000    ,500,500,500
BEGIN DESCRIPTION:
SANFERNANDO030 8.0
END DESCRIPTION:
XS GIS Cut Line= 3
      2797555.68      10242903.1      2797344.53     10242387.68
      2797305.69     10242203.12
#Sta/Elev= 30
    4443 1098.08  4481.7 1096.95  4487.1 1095.71  4511.1 1094.46  4559.1 1093.57
  4583.1 1091.93  4594.3 1089.71  4617.9 1087.36  4659.1 1085.16  4665.9 1083.43
  4683.5  1082.5  4686.8 1082.32  4695.3 1082.56  4719.3 1080.17  4788.8 1079.72
  4796.7 1078.17  4802.1 1079.88  4842.8 1078.08  4880.3 1078.37  4972.5  1077.1
  4986.2 1076.17  4991.4 1074.13  4991.8 1073.63  4996.9 1074.13  5009.8 1075.33
  5035.3 1078.89  5055.8 1084.82  5096.6 1091.63  5127.3 1095.77  5188.6 1100.19
#Mann= 7 ,-1 , 0
    4443     .12       0  4683.5     .05       0  4686.8     .12       0
  4880.3     .05       0  4991.4     .05       0  4996.9     .05       0
  5009.8     .12       0
Bank Sta=4991.4,4996.9
XS Rating Curve= 0 ,0
Exp/Cntr=0.3,0.1

Type RM Length L Ch R = 1 ,3500    ,500,500,500
BEGIN DESCRIPTION:
SANFERNANDO030 7.0
END DESCRIPTION:
XS GIS Cut Line= 3
      2797555.69      10242803.1      2797757.54     10242394.66
       2797555.7     10242053.14
#Sta/Elev= 30
  4544.4 1094.12  4603.3 1090.44  4642.6 1085.89  4648.2  1087.1    4665 1083.69
  4670.6 1083.84  4678.2 1082.22  4700.6 1080.96  4709.9 1079.51  4715.5 1080.45
  4732.3 1079.05  4737.9 1079.69  4799.7 1075.69  4805.2 1077.61  4822.1  1075.4
  4869.4 1073.93  4911.9 1070.93  4923.6  1072.3  4939.9 1072.67  4962.3 1071.34
  4979.2 1071.67  4995.3 1070.34  4995.8 1069.84  5000.8 1070.34  5016.3 1073.01
  5037.8 1074.52  5096.3 1075.62  5170.5 1080.18  5257.3 1083.28  5396.7  1091.9
#Mann= 4 ,-1 , 0
  4544.4     .12       0  4869.4     .05       0  4995.3     .05       0
  5000.8     .05       0
Bank Sta=4995.3,5000.8
XS Rating Curve= 0 ,0
Exp/Cntr=0.3,0.1

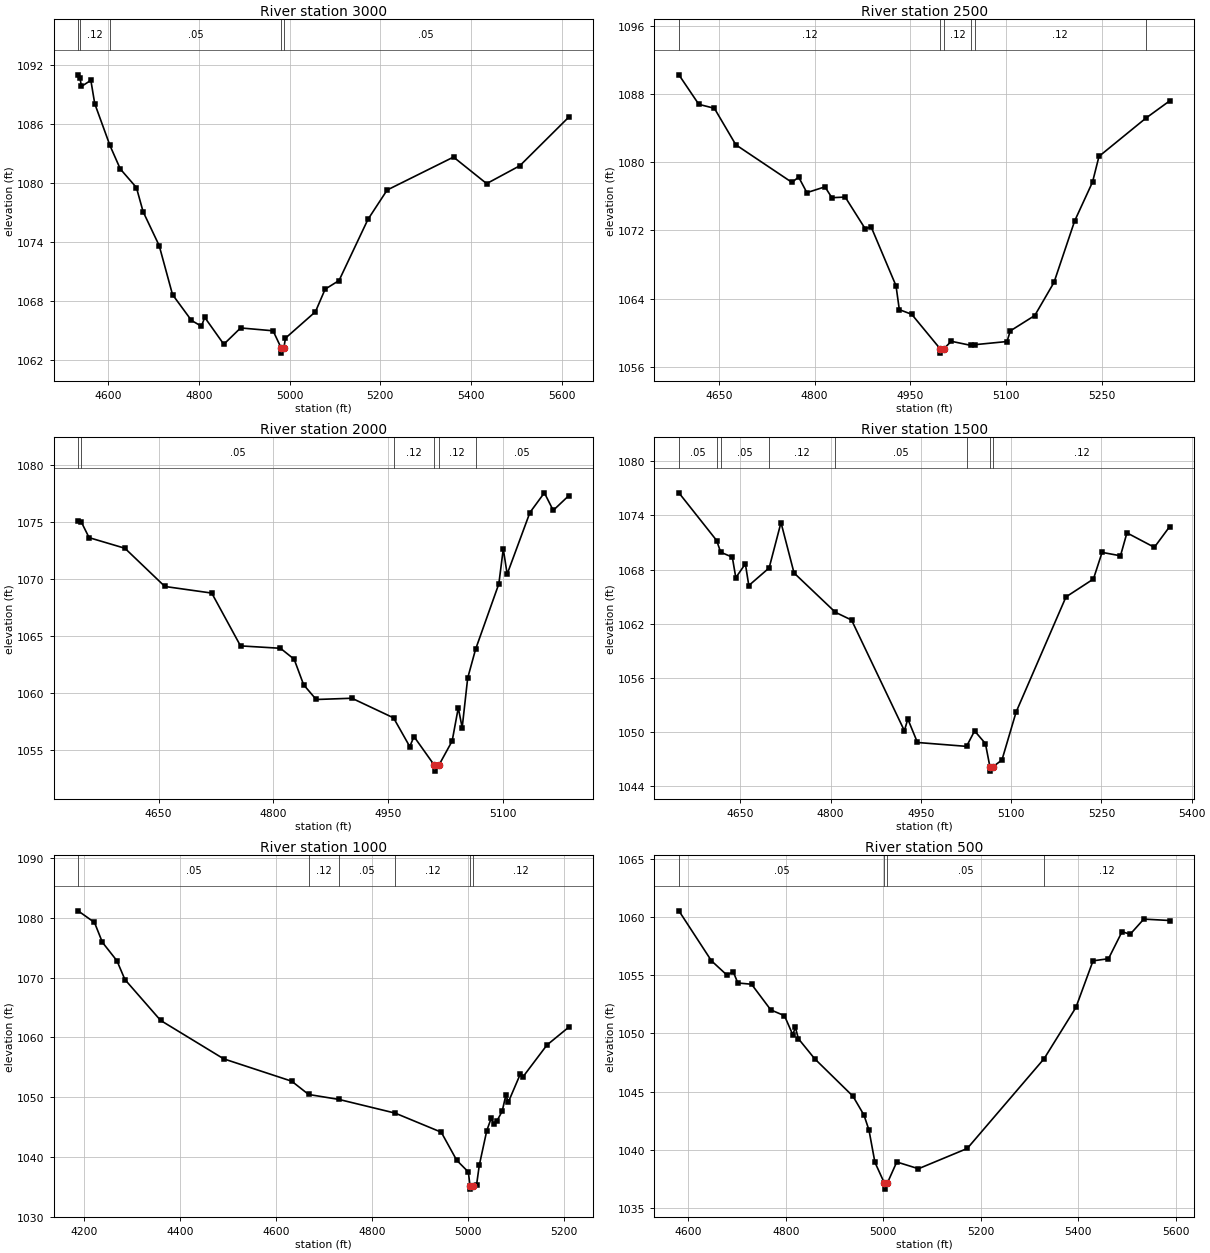
Type RM Length L Ch R = 1 ,3000    ,500,500,500
BEGIN DESCRIPTION:
SANFERNANDO030 6.0
END DESCRIPTION:
XS GIS Cut Line= 3
      2798605.69     10242553.12      2798228.16     10242278.75
      2797705.73     10241953.14
#Sta/Elev= 30
  4533.3    1091  4537.6 1090.67  4540.7 1089.82  4561.5 1090.44    4570 1088.08
  4603.5 1083.83  4626.4 1081.43    4662 1079.54  4676.7 1077.09  4712.2 1073.64
  4741.6 1068.66  4783.3 1066.04  4805.3 1065.44  4812.7 1066.34  4854.7 1063.61
  4891.8 1065.27  4963.4 1064.98  4981.5 1063.21  4981.9 1062.71  4987.1 1063.21
  4990.7 1064.23  5056.9 1066.92  5078.2 1069.21  5108.9 1070.09  5172.6  1076.3
    5215 1079.29  5361.4 1082.64  5434.5 1079.94  5507.7 1081.76  5615.6  1086.7
#Mann= 5 ,-1 , 0
  4533.3     .05       0  4537.6     .12       0  4603.5     .05       0
  4981.5     .05       0  4987.1     .05       0
Bank Sta=4981.5,4987.1
XS Rating Curve= 0 ,0
Exp/Cntr=0.3,0.1

Type RM Length L Ch R = 1 ,2500    ,500,500,500
BEGIN DESCRIPTION:
SANFERNANDO030 5.0
END DESCRIPTION:
XS GIS Cut Line= 3
      2798655.68     10242453.09      2798540.89     10242057.09
      2798505.69     10241703.13
#Sta/Elev= 30
  4587.7 1090.23  4618.9 1086.77  4643.2 1086.31  4676.8 1082.03  4764.7 1077.62
  4775.1 1078.25    4788 1076.42  4816.3  1077.1  4827.1 1075.83    4848  1075.9
  4879.2  1072.2  4888.7 1072.39  4927.5 1065.51  4932.7 1062.71  4952.1 1062.16
  4996.7 1058.11  4997.1 1057.61  5002.3 1058.11    5014    1059  5045.2 1058.51
  5050.9  1058.6  5101.3 1058.97  5106.3 1060.21  5144.7 1062.02  5174.8  1065.9
  5207.1  1073.1  5235.1 1077.66  5245.2 1080.67  5318.4 1085.14  5355.7 1087.17
#Mann= 6 ,-1 , 0
  4587.7     .12       0  4996.7     .07       0  5002.3     .12       0
  5045.2     .05       0  5050.9     .12       0  5318.4     .05       0
Bank Sta=4996.7,5002.3
XS Rating Curve= 0 ,0
Exp/Cntr=0.3,0.1

Type RM Length L Ch R = 1 ,2000    ,500,500,500
BEGIN DESCRIPTION:
SANFERNANDO030 4.0
END DESCRIPTION:
XS GIS Cut Line= 3
      2798705.68     10242253.13      2798888.57     10241836.18
      2798855.68     10241653.11
#Sta/Elev= 30
  4544.7 1075.06  4548.8 1075.02  4559.1 1073.63  4605.9  1072.7  4658.1 1069.35
  4719.4 1068.77    4757 1064.14  4809.2 1063.93  4827.1 1062.97  4839.5 1060.73
  4855.9 1059.44  4902.6 1059.55    4957 1057.83  4978.2 1055.31  4983.7 1056.19
  5010.5 1053.66  5010.9 1053.16  5016.1 1053.66  5033.6  1055.8  5041.6 1058.71
  5046.7 1056.97  5053.9 1061.32  5064.2 1063.84  5094.6 1069.58  5100.4 1072.64
  5105.5 1070.43  5135.2 1075.83  5154.1 1077.56  5165.7 1076.02    5186 1077.31
#Mann= 6 ,-1 , 0
  4544.7     .12       0  4548.8     .05       0    4957     .12       0
  5010.5     .07       0  5016.1     .12       0  5064.2     .05       0
Bank Sta=5010.5,5016.1
XS Rating Curve= 0 ,0
Exp/Cntr=0.3,0.1

Type RM Length L Ch R = 1 ,1500    ,500,500,500
BEGIN DESCRIPTION:
SANFERNANDO030 3.0
END DESCRIPTION:
XS GIS Cut Line= 3
       2798955.7     10242503.09      2799177.94     10242109.15
      2799105.68     10241753.11
#Sta/Elev= 30
  4547.7  1076.5  4610.5 1071.22  4617.1 1069.93  4636.5 1069.38  4642.3 1067.11
  4658.2 1068.64  4663.9 1066.24  4697.7 1068.19  4717.4 1073.21  4739.1 1067.63
  4807.8 1063.28  4834.7 1062.42  4922.5 1050.17  4928.2 1051.47  4944.2 1048.87
  5025.8 1048.44  5039.2 1050.15  5057.2 1048.75  5064.6  1046.2    5065  1045.7
  5070.2  1046.2  5084.7 1046.94  5108.2 1052.24  5191.1 1064.98  5236.7 1066.96
  5251.1 1069.91  5281.7 1069.53  5292.4 1072.07    5338 1070.47  5363.3 1072.75
#Mann= 8 ,-1 , 0
  4547.7     .05       0  4610.5     .12       0  4617.1     .05       0
  4697.7     .12       0  4807.8     .05       0  5025.8     .12       0
  5064.6     .05       0  5070.2     .12       0
Bank Sta=5064.6,5070.2
XS Rating Curve= 0 ,0
Exp/Cntr=0.3,0.1

Type RM Length L Ch R = 1 ,1000    ,500,500,500
BEGIN DESCRIPTION:
SANFERNANDO030 2.0
END DESCRIPTION:
XS GIS Cut Line= 3
      2799405.68     10242653.14      2799528.76      10241849.2
      2799455.67     10241653.08
#Sta/Elev= 30
  4186.7 1081.19  4220.9 1079.24  4237.3 1075.93  4267.7 1072.83  4284.3 1069.69
  4358.7 1062.85  4490.2 1056.42  4631.9 1052.68  4667.1 1050.46  4730.3 1049.63
  4847.5 1047.34  4943.5 1044.15  4975.8 1039.45    5000 1037.49  5003.6 1035.12
  5004.1 1034.62  5009.3 1035.12  5017.2 1035.35  5022.8 1038.61  5038.5 1044.43
  5047.8 1046.51  5053.1 1045.44  5059.9 1046.08  5070.5 1047.65  5078.1  1050.3
  5083.5 1049.21  5108.5 1053.91  5113.8  1053.4  5163.8 1058.73  5209.3 1061.72
#Mann= 6 ,-1 , 0
  4186.7     .05       0  4667.1     .12       0  4730.3     .05       0
  4847.5     .12       0  5003.6     .07       0  5009.3     .12       0
Bank Sta=5003.6,5009.3
XS Rating Curve= 0 ,0
Exp/Cntr=0.3,0.1

Type RM Length L Ch R = 1 ,500     ,0,0,0
BEGIN DESCRIPTION:
SANFERNANDO030 1.0
END DESCRIPTION:
XS GIS Cut Line= 3
      2799805.68     10242403.12      2799990.24     10242026.84
       2800255.7     10241503.07
#Sta/Elev= 30
  4580.9 1060.52  4647.7 1056.23  4679.3 1055.01  4692.3 1055.29  4701.8 1054.33
  4729.9 1054.22  4769.3 1052.02  4797.4 1051.52  4814.3  1049.9  4819.9 1050.51
  4825.9 1049.55  4859.3 1047.83  4937.9 1044.61  4960.4    1043  4970.7 1041.71
  4982.9 1038.94  5002.5 1037.14    5003 1036.64  5008.2 1037.14  5027.7 1038.97
  5072.2 1038.39  5172.3 1040.13    5330 1047.84  5395.1 1052.23  5430.2 1056.23
  5461.9 1056.41  5489.7 1058.73  5506.4 1058.51  5534.3 1059.81  5587.2 1059.69
#Mann= 4 ,-1 , 0
  4580.9     .05       0  5002.5     .03       0  5008.2     .05       0
    5330     .12       0
Bank Sta=5002.5,5008.2
XS Rating Curve= 0 ,0
Exp/Cntr=0.3,0.1

Chan Stop Cuts=-1
Use User Specified Reach Order=0
Composite Channel Slope=5