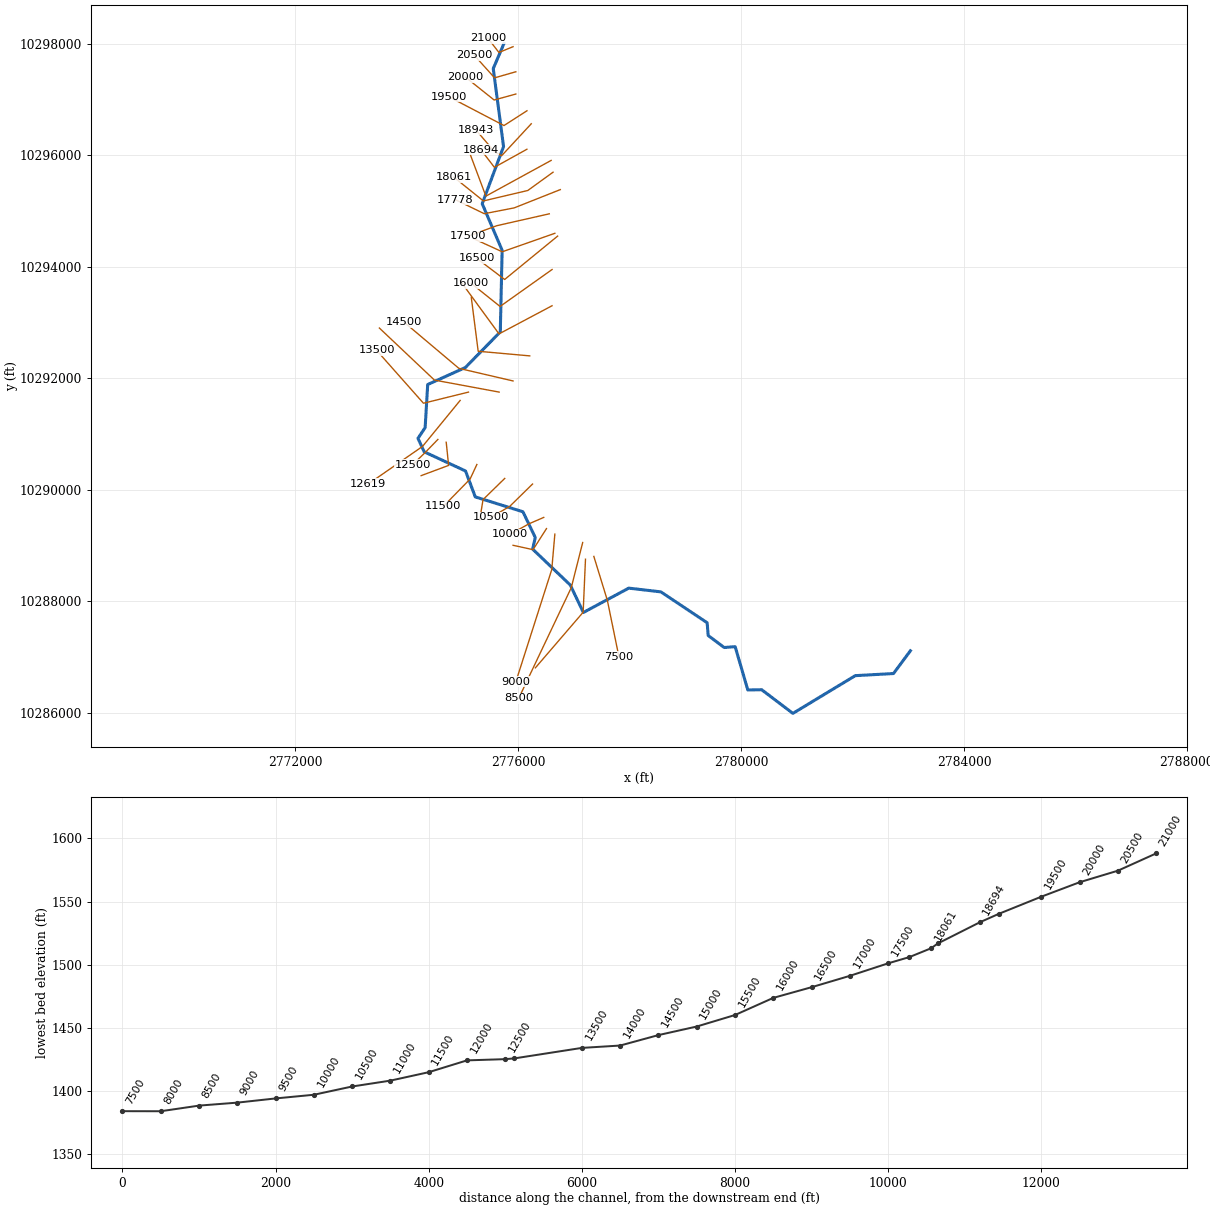
--- SANFERNANDO032.prj (project) ---

Proj Title=SANFERNANDO032 Base Level Engineering
Current Plan=p01
Default Exp/Contr=0.3,0.1
English Units
Geom File=g01
Flow File=f01
Plan File=p01
BEGIN DESCRIPTION:
SANFERNANDO032
END DESCRIPTION:

--- SANFERNANDO032.p01 (plan) ---

Plan Title=Multiple Run
Short Identifier=Multiple
Geom File=g01
Flow File=f01
Subcritical Flow
K Sum by GR= 0
Std Step Tol= 0.01
Critical Tol= 0.01
Num of Std Step Trials= 20
Max Error Tol= 0.3
Flow Tol Ratio= 0.001
Split Flow NTrial= 30
Split Flow Tol= 0.02
Split Flow Ratio= 0.02
Log Output Level= 0
Friction Slope Method= 1
Unsteady Friction Slope Method= 2
Unsteady Bridges Friction Slope Method= 1
Parabolic Critical Depth
Global Vel Dist=  1 , 1 , 1
Global Log Level= 0
CheckData=True
Encroach Param= -1, 0, 0, 0
BEGIN DESCRIPTION:
Multiple Run
END DESCRIPTION:

--- SANFERNANDO032.f01 (steady flow) ---

Flow Title=Multiple
Number of Profiles=7
Profile Names=10-year,25-year,50-year,1pct_min,100-year,1pct_plu,500-year
River Rch & RM= SANFERNANDO032,Reach-1,21000
     416     670    1359     990    1902    3653    2755
River Rch & RM= SANFERNANDO032,Reach-1,12500
     774    1306    2388    2018    3373    5638    4822
River Rch & RM= SANFERNANDO032,Reach-1,4000
    1096    1888    3535    2114    5045   12039    7170
Boundary for River Rch & Prof#=SANFERNANDO032,Reach-1,1
Up Type=0
Dn Type=3
Dn Slope=0.005
Boundary for River Rch & Prof#=SANFERNANDO032,Reach-1,2
Up Type=0
Dn Type=3
Dn Slope=0.005
Boundary for River Rch & Prof#=SANFERNANDO032,Reach-1,3
Up Type=0
Dn Type=3
Dn Slope=0.005
Boundary for River Rch & Prof#=SANFERNANDO032,Reach-1,4
Up Type=0
Dn Type=3
Dn Slope=0.005
Boundary for River Rch & Prof#=SANFERNANDO032,Reach-1,5
Up Type=0
Dn Type=3
Dn Slope=0.005
Boundary for River Rch & Prof#=SANFERNANDO032,Reach-1,6
Up Type=0
Dn Type=3
Dn Slope=0.005
Boundary for River Rch & Prof#=SANFERNANDO032,Reach-1,7
Up Type=0
Dn Type=3
Dn Slope=0.005

--- SANFERNANDO032.g01 (geometry) ---

Geom Title=Existing Conditions

River Reach=SANFERNANDO032,Reach-1
Reach XY= 30
      2775742.00     10298009.00      2775550.00     10297560.00
      2775735.00     10296160.00      2775351.75     10295135.00
      2775709.50     10294299.00      2775676.50     10292834.00
      2775049.00     10292194.00      2774373.25     10291889.00
      2774327.50     10291116.00      2774198.75     10290923.00
      2774310.25     10290681.00      2775052.50     10290337.00
      2775227.50     10289872.00      2776082.75     10289605.00
      2776304.25     10289143.00      2776257.25     10288934.00
      2776933.50     10288289.00      2777167.50     10287797.00
      2777982.50     10288234.00      2778559.25     10288167.00
      2779389.50     10287613.00      2779408.50     10287383.00
      2779696.00     10287168.00      2779892.25     10287184.00
      2780119.50     10286406.00      2780367.75     10286411.00
      2780928.75     10285986.00      2782048.50     10286663.00
      2782734.25     10286701.00      2783037.50     10287109.00

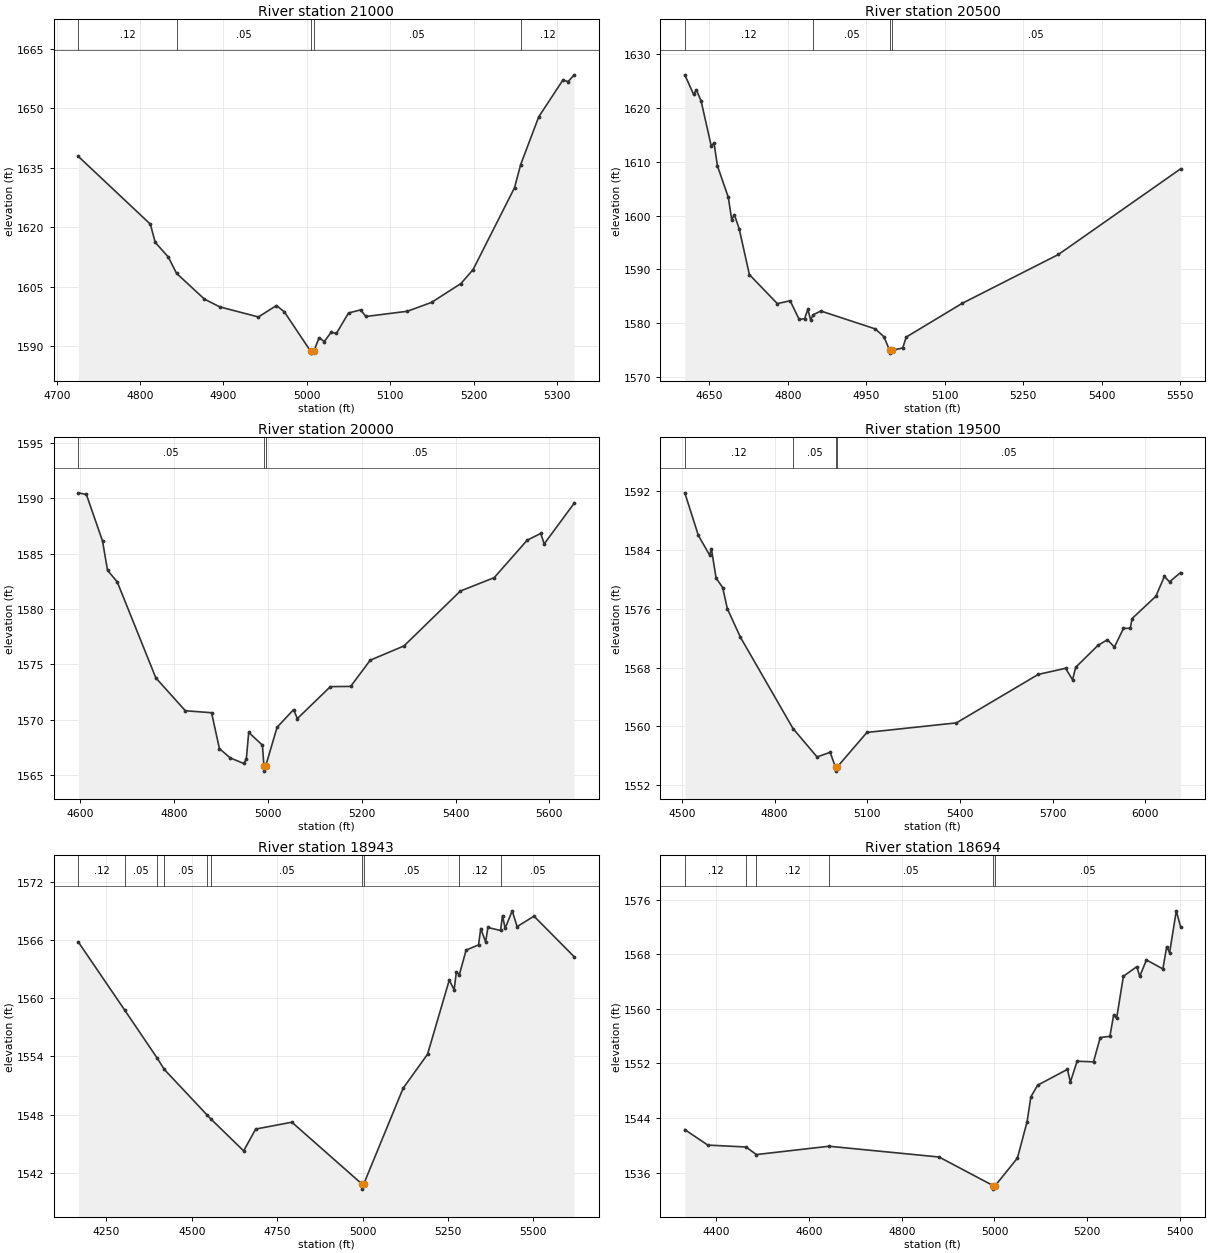
Type RM Length L Ch R = 1,21000,500,500,500
BEGIN DESCRIPTION:
SANFERNANDO032 42.0
END DESCRIPTION:
XS GIS Cut Line= 3
      2775905.68     10297953.11      2775651.94     10297849.43
      2775455.71     10298103.08
#Sta/Elev= 30
  4725.9 1637.88  4812.3 1620.76  4818.1 1616.18  4833.9 1612.44  4843.7 1608.34
  4877.1 1601.83  4895.5 1599.86  4941.9 1597.31  4963.6 1600.20  4973.0 1598.61
  5004.5 1588.67  5004.8 1588.17  5008.5 1588.67  5014.7 1592.06  5021.0 1591.09
  5029.2 1593.46  5035.5 1593.14  5050.0 1598.31  5064.5 1599.10  5070.8 1597.43
  5120.6 1598.75  5149.6 1600.99  5184.9 1605.76  5199.4 1609.27  5249.2 1629.99
  5256.5 1635.79  5278.2 1647.89  5307.2 1657.18  5313.5 1656.80  5320.7 1658.50
#Mann=5,-1,0
  4725.9    0.12       0  4843.7    0.05       0  5004.5    0.05       0
  5008.5    0.05       0  5256.5    0.12       0
Bank Sta=5004.5,5008.5
Exp/Cntr=0.3,0.1

Type RM Length L Ch R = 1,20500,500,500,500
BEGIN DESCRIPTION:
SANFERNANDO032 41.0
END DESCRIPTION:
XS GIS Cut Line= 3
      2775955.66     10297503.11      2775574.18     10297393.93
      2775205.72     10297803.08
#Sta/Elev= 30
  4603.2 1626.09  4620.1 1622.45  4625.3 1623.32  4634.4 1621.23  4653.8 1612.86
  4659.0 1613.44  4665.6 1609.20  4686.4 1603.36  4692.8 1599.23  4698.0 1600.15
  4707.2 1597.51  4726.6 1589.05  4780.0 1583.67  4804.5 1584.20  4821.6 1580.77
  4832.0 1580.85  4838.3 1582.61  4843.5 1580.72  4849.0 1581.63  4863.2 1582.30
  4967.2 1578.98  4983.8 1577.52  4994.6 1574.99  4994.9 1574.49  4998.6 1574.99
  5019.6 1575.45  5026.3 1577.47  5133.2 1583.72  5317.1 1592.78  5550.6 1608.66
#Mann=4,-1,0
  4603.2    0.12       0  4849.0    0.05       0  4994.6    0.05       0
  4998.6    0.05       0
Bank Sta=4994.6,4998.6
Exp/Cntr=0.3,0.1

Type RM Length L Ch R = 1,20000,500,500,500
BEGIN DESCRIPTION:
SANFERNANDO032 40.0
END DESCRIPTION:
XS GIS Cut Line= 3
      2775955.66     10297103.10      2775566.12     10296995.97
      2775055.71     10297403.09
#Sta/Elev= 30
  4596.0 1590.51  4613.2 1590.36  4647.6 1586.15  4658.2 1583.51  4678.9 1582.46
  4761.2 1573.78  4824.1 1570.81  4880.0 1570.63  4896.7 1567.39  4919.6 1566.55
  4948.6 1566.04  4954.0 1566.42  4959.2 1568.85  4988.4 1567.70  4991.6 1565.85
  4991.8 1565.35  4995.6 1565.85  5019.6 1569.31  5054.8 1570.91  5062.9 1570.10
  5133.3 1572.99  5176.5 1573.01  5218.2 1575.38  5290.2 1576.67  5410.3 1581.63
  5482.4 1582.84  5552.8 1586.23  5581.7 1586.84  5589.0 1585.89  5652.9 1589.57
#Mann=3,-1,0
  4596.0    0.05       0  4991.6    0.05       0  4995.6    0.05       0
Bank Sta=4991.6,4995.6
Exp/Cntr=0.3,0.1

Type RM Length L Ch R = 1,19500,557,557,557
BEGIN DESCRIPTION:
SANFERNANDO032 39.0
END DESCRIPTION:
XS GIS Cut Line= 3
      2776155.68     10296803.11      2775743.24     10296537.45
      2774755.67     10297053.12
#Sta/Elev= 30
  4509.4 1591.80  4553.3 1586.00  4589.6 1583.33  4595.6 1584.15  4610.7 1580.19
  4631.9 1578.91  4647.0 1576.04  4689.3 1572.15  4859.8 1559.70  4937.5 1555.84
  4979.8 1556.47  4997.4 1554.41  4997.6 1553.91  5001.4 1554.41  5098.8 1559.18
  5388.4 1560.48  5653.4 1567.08  5741.8 1567.91  5764.4 1566.35  5774.6 1568.05
  5846.5 1571.03  5877.2 1571.80  5899.7 1570.80  5929.2 1573.34  5951.3 1573.37
  5956.9 1574.68  6034.0 1577.72  6061.7 1580.43  6078.1 1579.68  6114.1 1580.95
#Mann=4,-1,0
  4509.4    0.12       0  4859.8    0.05       0  4997.4    0.03       0
  5001.4    0.05       0
Bank Sta=4997.4,5001.4
Exp/Cntr=0.3,0.1

Type RM Length L Ch R = 1,18943,249,249,249
BEGIN DESCRIPTION:
Mapping XS 69077bd2
END DESCRIPTION:
XS GIS Cut Line= 4
      2776232.67     10296569.88      2775701.40     10295996.94
      2775576.40     10296064.65      2775232.66     10296465.68
#Sta/Elev= 30
  4167.7 1565.81  4303.3 1558.79  4398.1 1553.85  4419.6 1552.65  4543.7 1547.99
  4555.5 1547.55  4651.7 1544.25  4686.9 1546.50  4792.9 1547.21  4999.0 1540.80
  4999.3 1540.30  5003.0 1540.80  5118.7 1550.72  5190.1 1554.22  5253.7 1561.88
  5268.0 1560.88  5274.6 1562.73  5283.2 1562.43  5303.1 1564.98  5339.4 1565.51
  5345.9 1567.20  5360.2 1565.81  5366.8 1567.31  5403.8 1567.00  5409.6 1568.53
  5417.3 1567.23  5438.1 1569.03  5452.4 1567.40  5501.8 1568.48  5619.4 1564.29
#Mann=10,-1,0
  4167.7    0.12       0  4303.3    0.05       0  4398.1    0.12       0
  4419.6    0.05       0  4543.7    0.12       0  4555.5    0.05       0
  4999.0    0.05       0  5003.0    0.05       0  5283.2    0.12       0
  5403.8    0.05       0
Bank Sta=4999,5003
Exp/Cntr=0.3,0.1

Type RM Length L Ch R = 1,18694,545,545,545
BEGIN DESCRIPTION:
Mapping XS c9fbdf11
END DESCRIPTION:
XS GIS Cut Line= 3
      2776154.27     10296112.05      2775570.25     10295788.00
      2775326.11     10296106.87
#Sta/Elev= 30
  4332.1 1542.30  4381.7 1540.03  4464.2 1539.75  4486.4 1538.64  4643.2 1539.86
  4880.6 1538.28  4997.6 1534.07  4997.9 1533.57  5001.6 1534.07  5049.6 1538.13
  5070.4 1543.45  5078.6 1547.11  5093.1 1548.81  5157.5 1551.14  5163.8 1549.28
  5178.3 1552.33  5213.7 1552.24  5228.2 1555.81  5249.0 1555.98  5257.3 1559.16
  5263.6 1558.63  5278.1 1564.79  5307.1 1566.20  5313.4 1564.78  5327.9 1567.19
  5363.3 1565.87  5371.5 1569.12  5377.8 1568.25  5392.3 1574.39  5401.6 1572.03
#Mann=6,-1,0
  4332.1    0.12       0  4464.2    0.05       0  4486.4    0.12       0
  4643.2    0.05       0  4997.6    0.05       0  5001.6    0.05       0
Bank Sta=4997.6,5001.6
Exp/Cntr=0.3,0.1

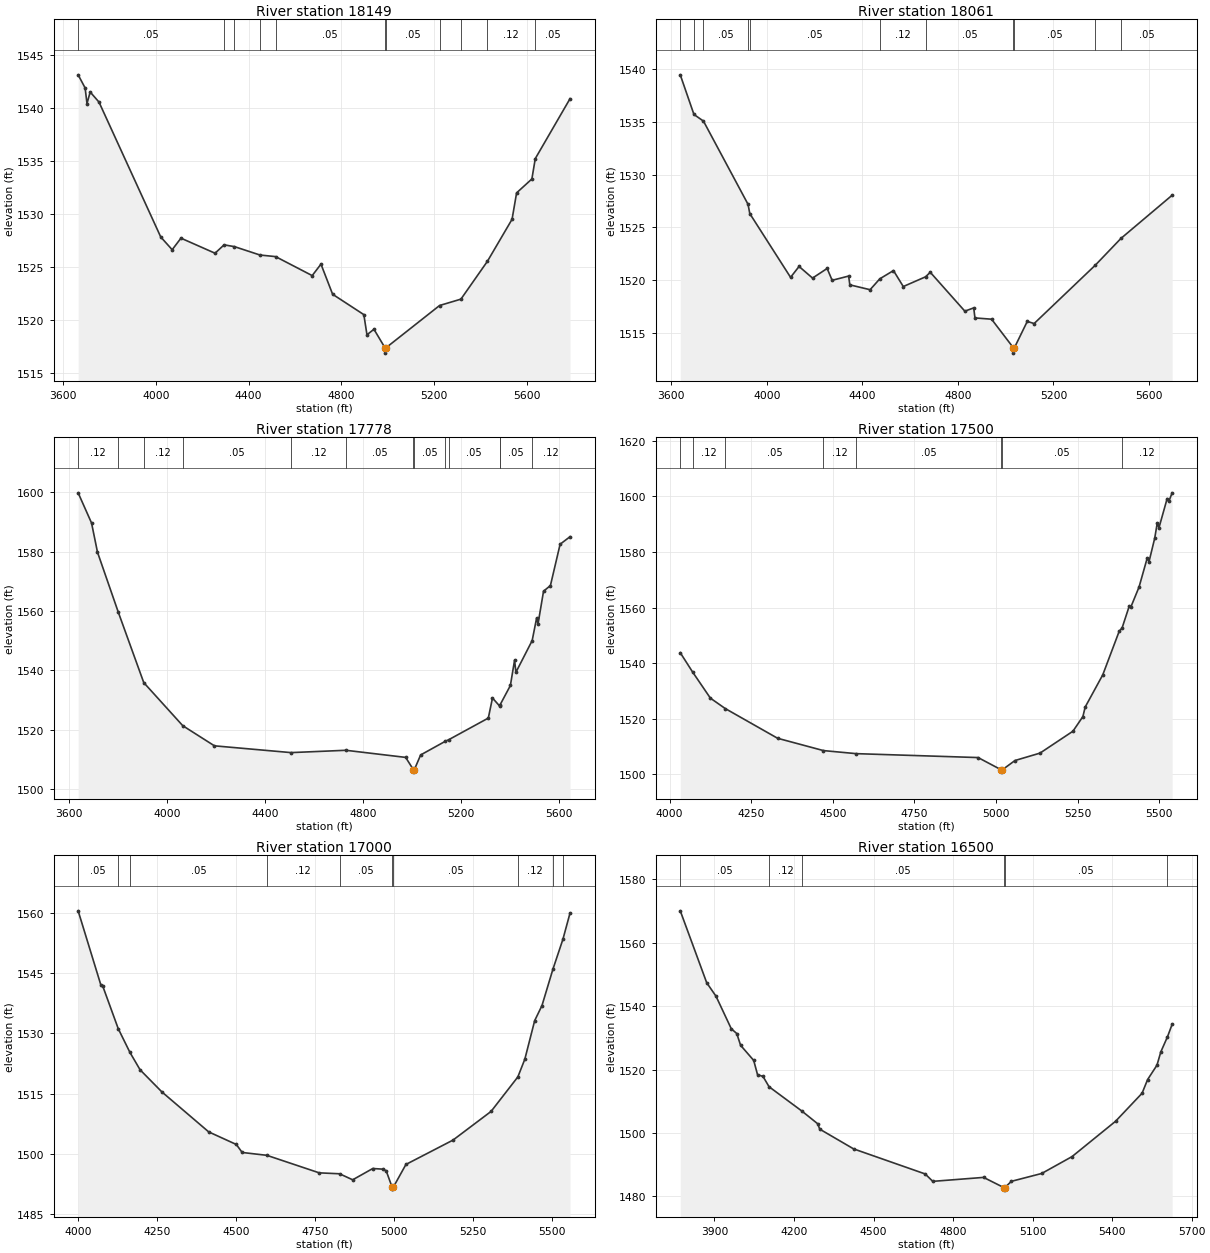
Type RM Length L Ch R = 1,18149,88,88,88
BEGIN DESCRIPTION:
SANFERNANDO032 37.0
END DESCRIPTION:
XS GIS Cut Line= 3
      2776589.17     10295911.53      2775417.80     10295270.69
      2775141.23     10296007.92
#Sta/Elev= 30
  3664.8 1543.15  3695.0 1541.91  3703.0 1540.44  3716.8 1541.53  3754.8 1540.58
  4021.3 1527.86  4070.6 1526.66  4108.5 1527.75  4255.6 1526.33  4294.7 1527.12
  4339.5 1526.95  4449.5 1526.16  4516.9 1526.01  4674.8 1524.22  4712.7 1525.30
  4763.0 1522.46  4897.7 1520.54  4911.2 1518.64  4941.3 1519.16  4989.0 1517.41
  4989.3 1516.91  4993.0 1517.41  5224.5 1521.40  5316.6 1522.00  5431.0 1525.57
  5537.3 1529.53  5556.9 1532.02  5622.8 1533.33  5637.5 1535.25  5787.4 1540.90
#Mann=11,-1,0
  3664.8    0.05       0  4294.7    0.12       0  4339.5    0.05       0
  4449.5    0.12       0  4516.9    0.05       0  4989.0    0.05       0
  4993.0    0.05       0  5224.5    0.12       0  5316.6    0.05       0
  5431.0    0.12       0  5637.5    0.05       0
Bank Sta=4989,4993
Exp/Cntr=0.3,0.1

Type RM Length L Ch R = 1,18061,283,283,283
BEGIN DESCRIPTION:
Mapping XS ba704586
END DESCRIPTION:
XS GIS Cut Line= 4
      2776623.31     10295700.09      2776170.15     10295371.94
      2775373.28     10295184.44      2774842.00     10295611.54
#Sta/Elev= 30
  3637.3 1539.44  3694.6 1535.69  3734.5 1535.06  3921.1 1527.19  3928.5 1526.31
  4099.2 1520.28  4134.8 1521.31  4191.2 1520.21  4252.4 1521.12  4273.3 1520.00
  4342.3 1520.40  4347.4 1519.57  4432.2 1519.11  4472.9 1520.14  4530.1 1520.92
  4571.2 1519.41  4664.5 1520.33  4684.2 1520.76  4829.0 1517.08  4866.2 1517.39
  4871.3 1516.44  4941.0 1516.32  5032.4 1513.61  5032.7 1513.11  5036.4 1513.61
  5090.4 1516.11  5119.2 1515.91  5375.3 1521.43  5482.6 1523.96  5697.1 1528.05
#Mann=11,-1,0
  3637.3    0.05       0  3694.6    0.12       0  3734.5    0.05       0
  3921.1    0.12       0  3928.5    0.05       0  4472.9    0.12       0
  4664.5    0.05       0  5032.4    0.05       0  5036.4    0.05       0
  5375.3    0.12       0  5482.6    0.05       0
Bank Sta=5032.4,5036.4
Exp/Cntr=0.3,0.1

Type RM Length L Ch R = 1,17778,278,278,278
BEGIN DESCRIPTION:
Mapping XS 47884da1
END DESCRIPTION:
XS GIS Cut Line= 4
      2776753.48     10295387.56      2775925.36     10295059.44
      2775388.90     10294955.27      2774873.25     10295205.29
#Sta/Elev= 30
  3636.3 1599.74  3691.1 1589.60  3715.4 1579.77  3800.0 1559.69  3904.5 1535.91
  4063.9 1521.42  4193.3 1514.65  4506.2 1512.37  4730.6 1513.15  4974.9 1510.76
  5006.4 1506.64  5006.6 1506.14  5010.4 1506.64  5036.1 1511.58  5136.8 1516.17
  5150.7 1516.70  5312.7 1523.98  5329.7 1530.74  5358.7 1528.05  5360.6 1528.41
  5402.9 1534.94  5420.0 1543.45  5425.5 1539.39  5491.9 1550.04  5510.3 1557.71
  5515.8 1555.62  5538.4 1566.66  5566.5 1568.55  5606.1 1582.45  5646.6 1584.98
#Mann=13,-1,0
  3636.3    0.12       0  3800.0    0.05       0  3904.5    0.12       0
  4063.9    0.05       0  4506.2    0.12       0  4730.6    0.05       0
  5006.4    0.05       0  5010.4    0.05       0  5136.8    0.12       0
  5150.7    0.05       0  5358.7    0.12       0  5360.6    0.05       0
  5491.9    0.12       0
Bank Sta=5006.4,5010.4
Exp/Cntr=0.3,0.1

Type RM Length L Ch R = 1,17500,500,500,500
BEGIN DESCRIPTION:
SANFERNANDO032 35.0
END DESCRIPTION:
XS GIS Cut Line= 3
      2776555.68     10294953.11      2775612.20     10294739.33
      2775105.65     10294553.10
#Sta/Elev= 30
  4032.6 1543.79  4070.1 1536.90  4124.9 1527.44  4170.4 1523.70  4330.9 1513.00
  4471.3 1508.57  4571.6 1507.47  4945.2 1506.06  5015.6 1501.68  5015.8 1501.18
  5019.6 1501.68  5058.2 1505.00  5134.8 1507.66  5235.7 1515.54  5266.2 1520.80
  5273.3 1524.25  5327.1 1535.82  5377.4 1551.49  5386.3 1552.68  5407.9 1560.44
  5413.2 1560.23  5438.3 1567.43  5463.5 1577.92  5468.8 1576.53  5486.4 1585.05
  5494.0 1590.40  5499.3 1588.75  5524.4 1599.25  5529.8 1598.33  5539.7 1601.32
#Mann=8,-1,0
  4032.6    0.05       0  4070.1    0.12       0  4170.4    0.05       0
  4471.3    0.12       0  4571.6    0.05       0  5015.6    0.05       0
  5019.6    0.05       0  5386.3    0.12       0
Bank Sta=5015.6,5019.6
Exp/Cntr=0.3,0.1

Type RM Length L Ch R = 1,17000,500,500,500
BEGIN DESCRIPTION:
SANFERNANDO032 34.0
END DESCRIPTION:
XS GIS Cut Line= 3
      2776655.66     10294603.10      2775711.49     10294271.52
      2775205.69     10294503.11
#Sta/Elev= 30
  3999.3 1560.52  4071.4 1542.03  4076.7 1541.90  4126.3 1531.19  4163.3 1525.29
  4195.4 1520.97  4264.2 1515.48  4412.6 1505.52  4500.0 1502.39  4518.6 1500.40
  4596.7 1499.69  4762.4 1495.33  4826.7 1495.10  4868.4 1493.60  4932.0 1496.41
  4963.8 1496.25  4974.4 1495.84  4993.1 1491.78  4993.4 1491.28  4997.1 1491.78
  5036.9 1497.42  5185.9 1503.48  5306.5 1510.62  5391.2 1519.20  5413.3 1523.62
  5444.5 1533.21  5467.5 1536.94  5502.0 1545.95  5533.9 1553.46  5556.3 1559.96
#Mann=10,-1,0
  3999.3    0.05       0  4126.3    0.12       0  4163.3    0.05       0
  4596.7    0.12       0  4826.7    0.05       0  4993.1    0.05       0
  4997.1    0.05       0  5391.2    0.12       0  5502.0    0.05       0
  5533.9    0.12       0
Bank Sta=4993.1,4997.1
Exp/Cntr=0.3,0.1

Type RM Length L Ch R = 1,16500,500,500,500
BEGIN DESCRIPTION:
SANFERNANDO032 33.0
END DESCRIPTION:
XS GIS Cut Line= 3
      2776705.67     10294553.10      2775754.79     10293774.62
      2775255.67     10294153.12
#Sta/Elev= 30
  3771.1 1570.08  3870.8 1547.40  3906.0 1543.13  3963.4 1532.90  3984.3 1531.36
  3998.6 1527.67  4048.1 1522.89  4062.5 1518.42  4083.3 1517.82  4106.0 1514.59
  4229.3 1506.95  4289.3 1502.92  4297.2 1501.21  4425.0 1494.98  4694.8 1487.08
  4723.6 1484.74  4915.2 1485.99  4991.4 1482.79  4991.7 1482.29  4995.4 1482.79
  5020.0 1484.75  5134.4 1487.23  5248.8 1492.55  5413.0 1503.70  5513.0 1512.54
  5533.8 1516.85  5569.2 1521.40  5583.7 1525.59  5608.8 1530.34  5626.4 1534.30
#Mann=6,-1,0
  3771.1    0.05       0  4106.0    0.12       0  4229.3    0.05       0
  4991.4    0.03       0  4995.4    0.05       0  5608.8    0.12       0
Bank Sta=4991.4,4995.4
Exp/Cntr=0.3,0.1

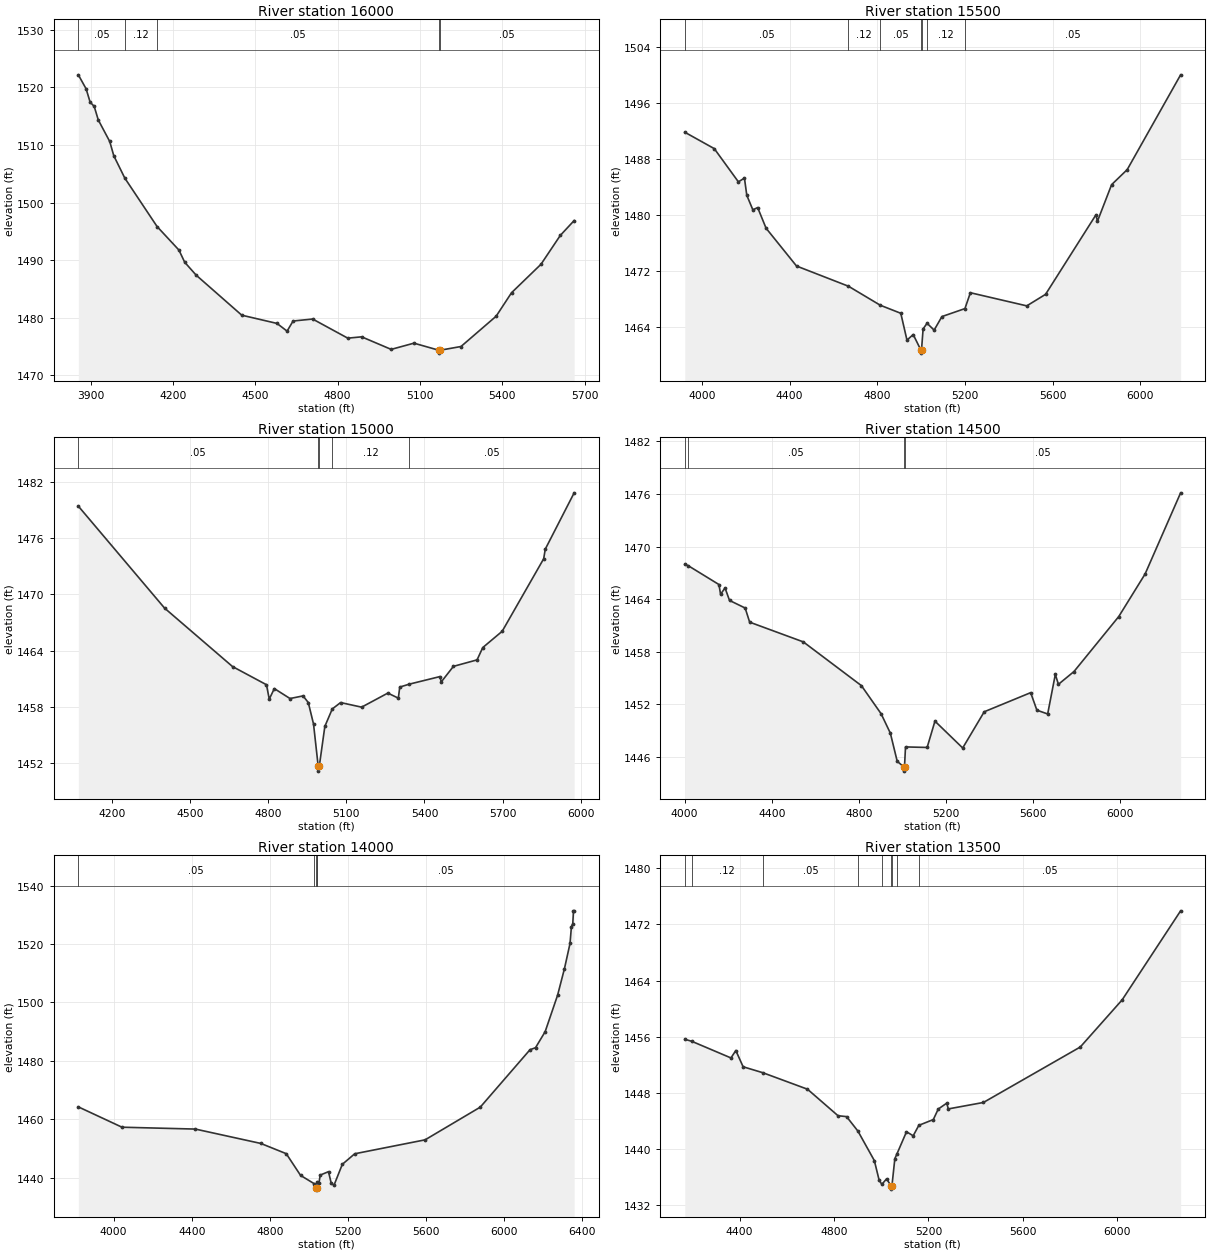
Type RM Length L Ch R = 1,16000,500,500,500
BEGIN DESCRIPTION:
SANFERNANDO032 32.0
END DESCRIPTION:
XS GIS Cut Line= 3
      2776605.66     10293953.09      2775672.40     10293290.24
      2775155.69     10293703.11
#Sta/Elev= 30
  3855.3 1522.18  3883.6 1519.75  3898.3 1517.43  3913.1 1516.70  3927.9 1514.35
  3969.7 1510.60  3984.4 1508.13  4024.6 1504.24  4142.1 1495.83  4221.8 1491.74
  4242.7 1489.63  4284.6 1487.38  4450.6 1480.43  4578.9 1479.00  4615.7 1477.66
  4637.6 1479.42  4708.9 1479.76  4836.8 1476.44  4887.3 1476.67  4994.9 1474.49
  5077.8 1475.57  5168.7 1474.34  5169.0 1473.84  5172.7 1474.34  5249.2 1474.99
  5377.2 1480.25  5433.3 1484.33  5540.5 1489.27  5611.0 1494.29  5661.4 1496.87
#Mann=5,-1,0
  3855.3    0.05       0  4024.6    0.12       0  4142.1    0.05       0
  5168.7    0.03       0  5172.7    0.05       0
Bank Sta=5168.7,5172.7
Exp/Cntr=0.3,0.1

Type RM Length L Ch R = 1,15500,500,500,500
BEGIN DESCRIPTION:
SANFERNANDO032 31.0
END DESCRIPTION:
XS GIS Cut Line= 3
      2776605.72     10293303.13      2775653.54     10292797.73
      2774955.69     10293753.10
#Sta/Elev= 30
  3922.0 1491.88  4056.5 1489.53  4166.4 1484.78  4194.0 1485.32  4204.7 1482.86
  4232.3 1480.78  4254.3 1481.10  4292.6 1478.15  4431.5 1472.74  4668.3 1469.85
  4813.5 1467.13  4907.0 1465.98  4935.2 1462.14  4963.6 1462.94  4997.6 1460.78
  4997.8 1460.28  5001.6 1460.78  5008.8 1463.75  5026.8 1464.55  5059.0 1463.57
  5094.6 1465.51  5199.5 1466.65  5224.3 1468.92  5481.5 1467.04  5567.2 1468.69
  5797.3 1480.08  5803.5 1479.12  5868.4 1484.38  5939.5 1486.53  6183.1 1500.09
#Mann=7,-1,0
  3922.0    0.05       0  4668.3    0.12       0  4813.5    0.05       0
  4997.6    0.05       0  5001.6    0.05       0  5026.8    0.12       0
  5199.5    0.05       0
Bank Sta=4997.6,5001.6
Exp/Cntr=0.3,0.1

Type RM Length L Ch R = 1,15000,500,500,500
BEGIN DESCRIPTION:
SANFERNANDO032 30.0
END DESCRIPTION:
XS GIS Cut Line= 3
      2776205.64     10292403.12      2775279.44     10292486.00
      2775155.68     10293453.12
#Sta/Elev= 30
  4070.1 1479.41  4401.4 1468.54  4662.4 1462.31  4792.9 1460.37  4803.6 1458.84
  4823.1 1459.96  4883.3 1458.90  4933.5 1459.18  4953.6 1458.47  4973.7 1456.18
  4991.7 1451.66  4992.0 1451.16  4995.7 1451.66  5017.2 1455.93  5045.7 1457.79
  5077.7 1458.47  5158.4 1457.98  5259.2 1459.48  5299.5 1458.94  5305.0 1460.12
  5341.2 1460.43  5459.4 1461.24  5464.4 1460.67  5511.2 1462.33  5602.0 1463.02
  5623.8 1464.33  5698.5 1466.07  5857.9 1473.80  5864.1 1474.83  5975.0 1480.83
#Mann=5,-1,0
  4070.1    0.05       0  4991.7    0.05       0  4995.7    0.05       0
  5045.7    0.12       0  5341.2    0.05       0
Bank Sta=4991.7,4995.7
Exp/Cntr=0.3,0.1

Type RM Length L Ch R = 1,14500,500,500,500
BEGIN DESCRIPTION:
SANFERNANDO032 29.0
END DESCRIPTION:
XS GIS Cut Line= 3
      2775905.68     10291953.11      2774932.60     10292179.64
      2773955.67     10293003.12
#Sta/Elev= 30
  4000.9 1467.98  4016.0 1467.83  4157.7 1465.67  4165.2 1464.56  4185.7 1465.28
  4206.2 1463.86  4278.1 1462.99  4298.7 1461.38  4545.1 1459.13  4811.9 1454.14
  4902.2 1450.94  4944.8 1448.72  4976.3 1445.51  5005.8 1444.89  5006.1 1444.39
  5009.8 1444.89  5014.4 1447.15  5113.7 1447.09  5149.6 1450.09  5277.0 1447.03
  5375.9 1451.16  5589.1 1453.34  5617.7 1451.34  5667.2 1450.91  5702.3 1455.42
  5716.6 1454.29  5788.1 1455.75  5993.6 1462.02  6114.5 1466.87  6277.7 1476.13
#Mann=4,-1,0
  4000.9    0.12       0  4016.0    0.05       0  5005.8    0.05       0
  5009.8    0.05       0
Bank Sta=5005.8,5009.8
Exp/Cntr=0.3,0.1

Type RM Length L Ch R = 1,14000,500,500,500
BEGIN DESCRIPTION:
SANFERNANDO032 28.0
END DESCRIPTION:
XS GIS Cut Line= 3
      2775655.72     10291753.11      2774494.35     10291968.65
      2773505.68     10292903.11
#Sta/Elev= 30
  3818.8 1464.27  4042.6 1457.31  4418.9 1456.67  4754.5 1451.75  4884.6 1448.25
  4958.0 1440.82  5027.6 1437.99  5035.7 1436.62  5036.0 1436.12  5039.7 1436.62
  5044.6 1438.67  5051.9 1438.10  5058.8 1440.93  5101.2 1442.10  5115.4 1438.05
  5129.6 1437.49  5172.0 1444.61  5235.6 1448.22  5596.4 1452.99  5879.2 1464.18
  6134.1 1483.83  6162.4 1484.52  6211.7 1490.00  6275.6 1502.51  6310.8 1511.61
  6339.2 1520.19  6346.4 1525.97  6353.3 1526.98  6357.0 1531.36  6360.4 1531.36
#Mann=5,-1,0
  3818.8    0.05       0  5027.6    0.12       0  5035.7    0.03       0
  5039.7    0.12       0  5044.6    0.05       0
Bank Sta=5035.7,5039.7
Exp/Cntr=0.3,0.1

Type RM Length L Ch R = 1,13500,881,881,881
BEGIN DESCRIPTION:
SANFERNANDO032 27.0
END DESCRIPTION:
XS GIS Cut Line= 3
      2775105.64     10291753.10      2774297.44     10291553.01
      2773455.72     10292503.07
#Sta/Elev= 30
  4167.4 1455.62  4196.4 1455.34  4363.1 1452.96  4383.7 1454.02  4414.6 1451.70
  4498.4 1450.85  4687.5 1448.50  4816.9 1444.72  4853.2 1444.59  4901.2 1442.53
  4970.9 1438.32  4991.5 1435.49  5002.9 1434.94  5022.7 1435.71  5041.6 1434.75
  5041.9 1434.25  5045.6 1434.75  5057.8 1438.59  5067.2 1439.31  5107.2 1442.43
  5135.6 1441.86  5159.6 1443.35  5220.9 1444.17  5241.8 1445.67  5277.8 1446.51
  5284.5 1445.69  5433.4 1446.61  5844.0 1454.52  6021.4 1461.24  6269.3 1473.94
#Mann=9,-1,0
  4167.4    0.05       0  4196.4    0.12       0  4498.4    0.05       0
  4901.2    0.12       0  5002.9    0.05       0  5041.6    0.07       0
  5045.6    0.05       0  5067.2    0.12       0  5159.6    0.05       0
Bank Sta=5041.6,5045.6
Exp/Cntr=0.3,0.1

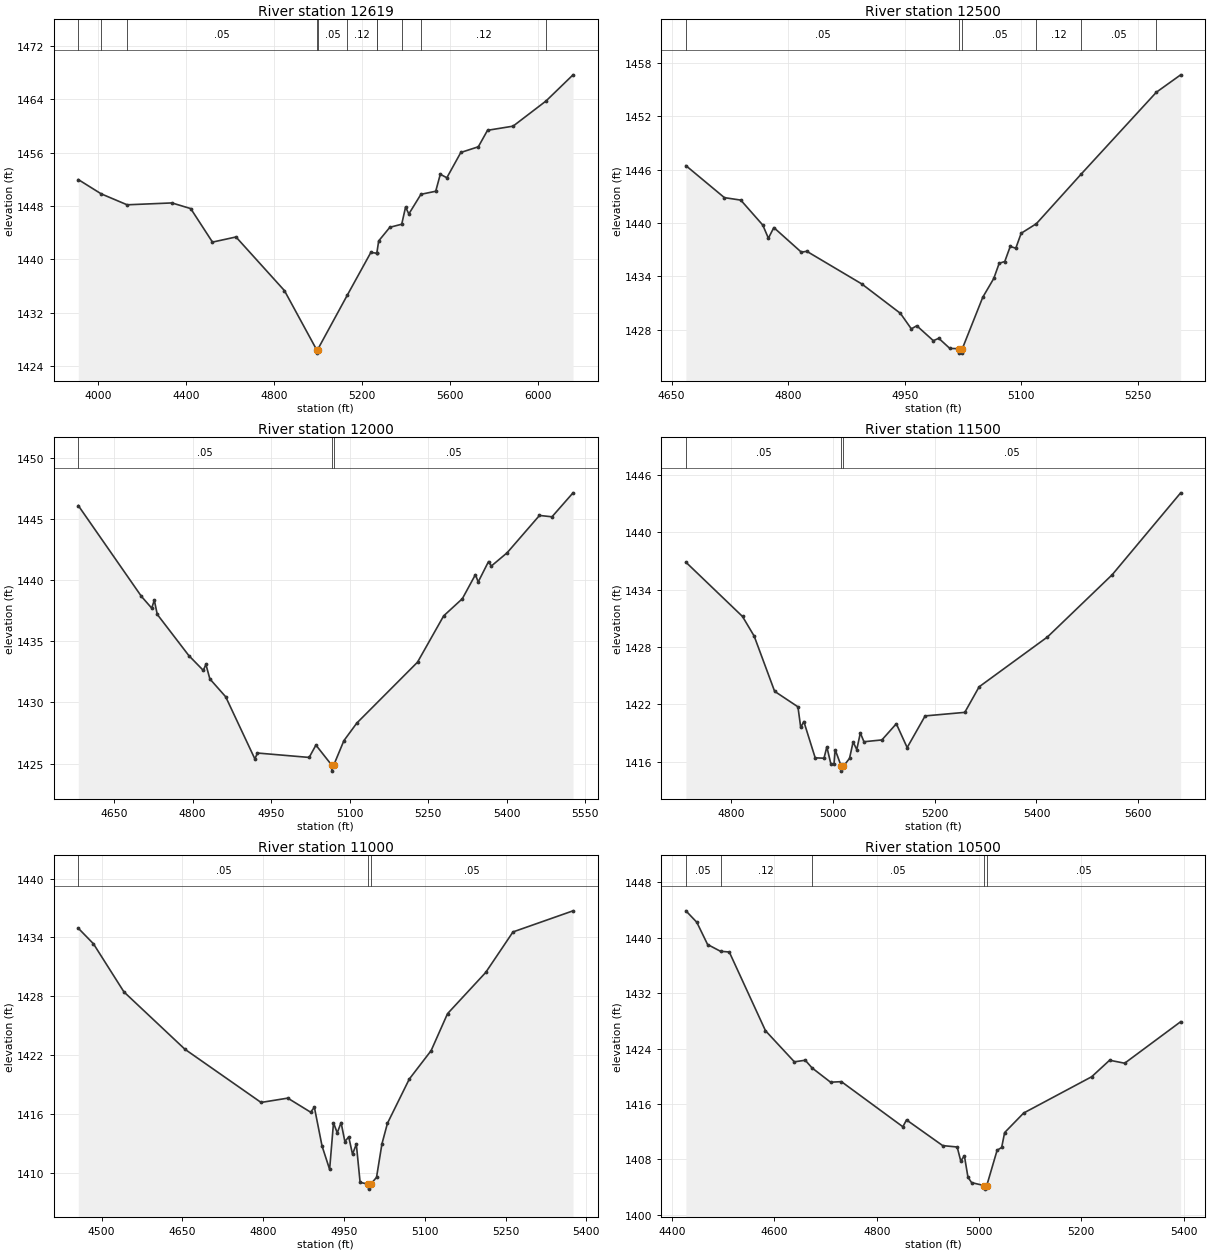
Type RM Length L Ch R = 1,12619,119,119,119
BEGIN DESCRIPTION:
SANFERNANDO032 26.0
END DESCRIPTION:
XS GIS Cut Line= 3
      2774955.68     10291603.10      2774280.68     10290778.11
      2773305.68     10290103.11
#Sta/Elev= 30
  3908.0 1451.95  4012.3 1449.81  4130.3 1448.17  4334.4 1448.45  4419.8 1447.60
  4518.8 1442.58  4625.8 1443.35  4846.2 1435.32  4992.9 1426.45  4993.1 1425.95
  4996.9 1426.45  5132.8 1434.66  5239.5 1441.03  5266.0 1440.92  5266.5 1440.88
  5275.3 1442.76  5326.0 1444.80  5380.0 1445.26  5397.6 1447.83  5412.5 1446.80
  5467.5 1449.74  5534.8 1450.20  5555.7 1452.75  5585.4 1452.22  5649.0 1456.01
  5728.7 1456.86  5770.6 1459.33  5886.8 1459.95  6036.8 1463.72  6159.8 1467.64
#Mann=11,-1,0
  3908.0    0.05       0  4012.3    0.12       0  4130.3    0.05       0
  4992.9    0.05       0  4996.9    0.05       0  5132.8    0.12       0
  5266.0    0.05       0  5266.5    0.12       0  5380.0    0.05       0
  5467.5    0.12       0  6036.8    0.05       0
Bank Sta=4992.9,4996.9
Exp/Cntr=0.3,0.1

Type RM Length L Ch R = 1,12500,500,500,500
BEGIN DESCRIPTION:
SANFERNANDO032 25.0
END DESCRIPTION:
XS GIS Cut Line= 3
      2774555.68     10290903.10      2774324.97     10290665.06
      2774105.66     10290453.09
#Sta/Elev= 30
  4668.5 1446.45  4718.0 1442.85  4739.1 1442.57  4767.4 1439.76  4774.6 1438.28
  4781.6 1439.48  4817.0 1436.71  4824.0 1436.81  4894.7 1433.14  4944.4 1429.83
  4958.5 1428.08  4965.5 1428.43  4986.8 1426.75  4993.8 1427.02  5008.0 1425.88
  5020.1 1425.85  5020.4 1425.35  5023.9 1425.35  5024.1 1425.85  5050.4 1431.64
  5064.6 1433.76  5071.5 1435.46  5078.7 1435.66  5085.7 1437.35  5092.9 1437.16
  5099.8 1438.84  5119.4 1439.92  5176.9 1445.49  5273.7 1454.71  5305.0 1456.67
#Mann=6,-1,0
  4668.5    0.05       0  5020.1    0.05       0  5024.1    0.05       0
  5119.4    0.12       0  5176.9    0.05       0  5273.7    0.12       0
Bank Sta=5020.1,5024.1
Exp/Cntr=0.3,0.1

Type RM Length L Ch R = 1,12000,500,500,500
BEGIN DESCRIPTION:
SANFERNANDO032 24.0
END DESCRIPTION:
XS GIS Cut Line= 3
      2774705.69     10290853.09      2774749.04     10290437.14
      2774255.65     10290253.10
#Sta/Elev= 30
  4581.8 1446.10  4702.4 1438.67  4722.0 1437.71  4727.0 1438.36  4732.6 1437.20
  4792.9 1433.83  4820.5 1432.62  4825.5 1433.11  4833.1 1431.92  4863.3 1430.46
  4919.0 1425.38  4924.0 1425.86  5022.7 1425.50  5035.6 1426.51  5065.6 1424.88
  5065.9 1424.38  5069.7 1424.88  5089.0 1426.87  5113.7 1428.31  5229.6 1433.29
  5279.6 1437.08  5315.2 1438.48  5340.2 1440.45  5345.5 1439.85  5365.2 1441.52
  5370.5 1441.15  5400.8 1442.24  5462.5 1445.29  5486.4 1445.18  5526.6 1447.14
#Mann=3,-1,0
  4581.8    0.05       0  5065.6    0.05       0  5069.7    0.05       0
Bank Sta=5065.6,5069.7
Exp/Cntr=0.3,0.1

Type RM Length L Ch R = 1,11500,500,500,500
BEGIN DESCRIPTION:
SANFERNANDO032 23.0
END DESCRIPTION:
XS GIS Cut Line= 3
      2775255.70     10290453.14      2775133.79     10290191.45
      2774655.70     10289703.12
#Sta/Elev= 30
  4711.3 1436.86  4822.5 1431.19  4845.4 1429.14  4885.6 1423.37  4931.4 1421.75
  4936.9 1419.59  4943.0 1420.21  4965.3 1416.42  4982.6 1416.38  4988.2 1417.56
  4996.3 1415.74  5002.2 1415.74  5004.6 1417.26  5016.6 1415.53  5016.9 1415.03
  5020.7 1415.53  5032.8 1416.37  5039.8 1418.08  5047.0 1417.28  5054.0 1419.02
  5061.1 1418.10  5096.4 1418.29  5124.7 1419.98  5146.0 1417.49  5181.3 1420.80
  5259.2 1421.17  5287.4 1423.84  5421.7 1429.05  5549.0 1435.56  5683.4 1444.11
#Mann=3,-1,0
  4711.3    0.05       0  5016.6    0.05       0  5020.7    0.05       0
Bank Sta=5016.6,5020.7
Exp/Cntr=0.3,0.1

Type RM Length L Ch R = 1,11000,500,500,500
BEGIN DESCRIPTION:
SANFERNANDO032 22.0
END DESCRIPTION:
XS GIS Cut Line= 3
      2775755.70     10290203.13      2775367.04     10289823.36
      2775305.68     10289453.11
#Sta/Elev= 30
  4456.6 1434.94  4484.8 1433.35  4541.4 1428.45  4654.6 1422.61  4796.0 1417.19
  4845.6 1417.63  4888.0 1416.20  4895.0 1416.70  4909.2 1412.76  4923.3 1410.37
  4930.5 1415.11  4937.5 1414.09  4944.6 1415.14  4951.6 1413.21  4958.8 1413.68
  4965.8 1411.92  4972.9 1412.94  4979.9 1409.05  4995.4 1408.86  4995.6 1408.36
  4999.6 1408.86  5010.4 1409.56  5020.5 1412.98  5030.7 1415.07  5071.2 1419.57
  5111.8 1422.47  5142.2 1426.23  5213.1 1430.43  5263.8 1434.56  5375.3 1436.71
#Mann=3,-1,0
  4456.6    0.05       0  4995.4    0.05       0  4999.6    0.05       0
Bank Sta=4995.4,4999.6
Exp/Cntr=0.3,0.1

Type RM Length L Ch R = 1,10500,500,500,500
BEGIN DESCRIPTION:
SANFERNANDO032 21.0
END DESCRIPTION:
XS GIS Cut Line= 3
      2776255.71     10290103.14      2775846.21     10289702.06
      2775505.67     10289503.10
#Sta/Elev= 30
  4426.8 1443.87  4448.1 1442.22  4469.2 1439.01  4494.5 1438.03  4511.6 1437.93
  4582.4 1426.57  4638.9 1422.08  4660.2 1422.31  4673.5 1421.20  4709.7 1419.14
  4730.9 1419.22  4851.1 1412.71  4858.2 1413.70  4929.0 1409.99  4957.3 1409.79
  4964.3 1407.77  4971.4 1408.52  4978.4 1405.43  4985.5 1404.65  5010.7 1404.21
  5011.0 1403.71  5015.1 1404.21  5035.4 1409.32  5044.3 1409.72  5050.1 1411.87
  5087.3 1414.69  5220.4 1419.93  5255.4 1422.31  5284.9 1421.88  5394.4 1427.87
#Mann=5,-1,0
  4426.8    0.05       0  4494.5    0.12       0  4673.5    0.05       0
  5010.7    0.05       0  5015.1    0.05       0
Bank Sta=5010.7,5015.1
Exp/Cntr=0.3,0.1

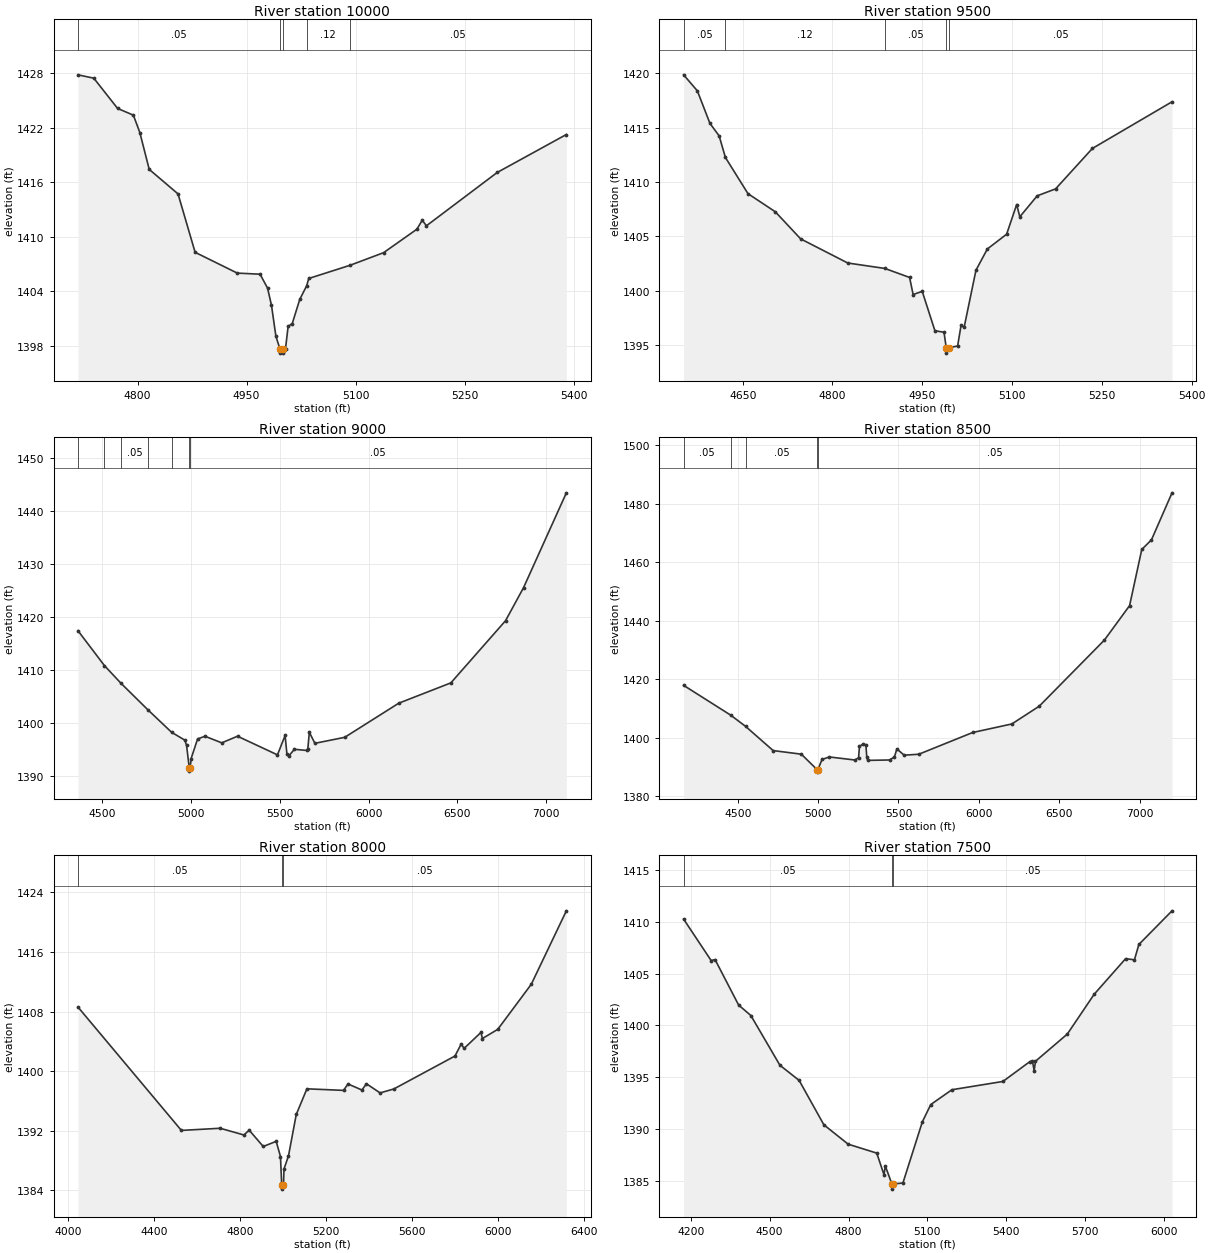
Type RM Length L Ch R = 1,10000,500,500,500
BEGIN DESCRIPTION:
SANFERNANDO032 20.0
END DESCRIPTION:
XS GIS Cut Line= 3
      2776455.70     10289503.12      2776196.80     10289391.60
      2775855.70     10289203.12
#Sta/Elev= 30
  4718.1 1427.81  4739.9 1427.44  4772.6 1424.11  4794.3 1423.37  4803.2 1421.45
  4816.1 1417.40  4855.7 1414.70  4879.2 1408.27  4937.2 1405.98  4968.5 1405.86
  4978.8 1404.33  4984.2 1402.44  4990.3 1399.02  4995.7 1397.67  4996.0 1397.17
  4999.8 1397.17  5000.1 1397.67  5003.5 1397.67  5007.1 1400.11  5012.8 1400.43
  5023.1 1403.09  5032.5 1404.57  5035.5 1405.39  5092.2 1406.84  5138.4 1408.23
  5184.1 1410.81  5191.5 1411.80  5197.3 1411.19  5294.6 1417.06  5389.7 1421.24
#Mann=5,-1,0
  4718.1    0.05       0  4995.7    0.05       0  5000.1    0.05       0
  5032.5    0.12       0  5092.2    0.05       0
Bank Sta=4995.7,5000.1
Exp/Cntr=0.3,0.1

Type RM Length L Ch R = 1,9500,500,500,500
BEGIN DESCRIPTION:
SANFERNANDO032 19.0
END DESCRIPTION:
XS GIS Cut Line= 3
      2776505.70     10289303.13      2776264.45     10288924.81
      2775905.70     10289003.11
#Sta/Elev= 30
  4551.3 1419.86  4574.2 1418.39  4595.3 1415.39  4610.6 1414.25  4621.1 1412.26
  4658.8 1408.93  4704.5 1407.26  4746.8 1404.77  4825.5 1402.55  4887.5 1402.05
  4928.8 1401.22  4934.7 1399.65  4949.9 1399.94  4971.1 1396.32  4986.3 1396.18
  4990.0 1394.76  4990.3 1394.26  4994.5 1394.76  5009.0 1394.91  5014.8 1396.82
  5019.9 1396.63  5039.7 1401.89  5058.7 1403.84  5090.9 1405.20  5107.7 1407.93
  5112.9 1406.80  5142.0 1408.73  5172.7 1409.37  5234.2 1413.09  5367.2 1417.38
#Mann=5,-1,0
  4551.3    0.05       0  4621.1    0.12       0  4887.5    0.05       0
  4990.0    0.05       0  4994.5    0.05       0
Bank Sta=4990,4994.5
Exp/Cntr=0.3,0.1

Type RM Length L Ch R = 1,9000,500,500,500
BEGIN DESCRIPTION:
SANFERNANDO032 18.0
END DESCRIPTION:
XS GIS Cut Line= 3
      2776655.68     10289203.11      2776600.20     10288567.43
      2775955.69     10286553.13
#Sta/Elev= 30
  4361.9 1417.45  4511.3 1410.85  4604.5 1407.52  4756.9 1402.49  4889.8 1398.27
  4964.2 1396.79  4974.2 1395.78  4989.6 1391.44  4989.9 1390.94  4994.1 1391.44
  4999.7 1393.31  5036.3 1397.02  5078.0 1397.52  5172.5 1396.28  5261.3 1397.53
  5486.4 1394.01  5529.5 1397.67  5540.0 1394.08  5550.5 1393.82  5582.0 1395.06
  5652.5 1394.84  5657.7 1395.15  5666.0 1398.27  5697.5 1396.19  5865.5 1397.32
  6170.0 1403.76  6464.0 1407.60  6772.0 1419.33  6873.7 1425.58  7114.9 1443.47
#Mann=7,-1,0
  4361.9    0.05       0  4511.3    0.12       0  4604.5    0.05       0
  4756.9    0.12       0  4889.8    0.05       0  4989.6    0.05       0
  4994.1    0.05       0
Bank Sta=4989.6,4994.1
Exp/Cntr=0.3,0.1

Type RM Length L Ch R = 1,8500,500,500,500
BEGIN DESCRIPTION:
SANFERNANDO032 17.0
END DESCRIPTION:
XS GIS Cut Line= 3
      2777155.69     10289053.15      2776950.37     10288242.03
      2776005.67     10286253.08
#Sta/Elev= 30
  4163.3 1417.89  4456.3 1407.70  4548.9 1403.87  4720.4 1395.60  4895.7 1394.37
  4993.9 1389.08  4994.3 1388.58  4998.5 1389.08  5024.5 1392.57  5070.0 1393.42
  5229.1 1392.38  5251.8 1393.15  5257.3 1397.05  5280.0 1397.82  5297.2 1397.59
  5302.8 1393.42  5308.8 1392.25  5444.6 1392.39  5474.8 1393.42  5490.1 1396.15
  5535.5 1394.03  5626.4 1394.35  5962.0 1401.78  6205.5 1404.70  6375.8 1410.77
  6781.2 1433.36  6937.8 1445.12  7013.7 1464.31  7074.1 1467.62  7201.9 1483.67
#Mann=5,-1,0
  4163.3    0.05       0  4456.3    0.12       0  4548.9    0.05       0
  4993.9    0.05       0  4998.5    0.05       0
Bank Sta=4993.9,4998.5
Exp/Cntr=0.3,0.1

Type RM Length L Ch R = 1,8000,500,500,500
BEGIN DESCRIPTION:
SANFERNANDO032 16.0
END DESCRIPTION:
XS GIS Cut Line= 3
      2777205.68     10288753.12      2777163.76     10287801.24
      2776305.66     10286803.09
#Sta/Elev= 30
  4047.2 1408.60  4527.7 1392.02  4707.8 1392.31  4818.0 1391.41  4842.8 1392.05
  4908.0 1389.86  4968.1 1390.55  4988.1 1388.51  4993.9 1384.63  4994.3 1384.13
  4999.3 1384.63  5002.1 1384.63  5004.4 1386.83  5025.3 1388.60  5061.5 1394.17
  5110.9 1397.61  5280.9 1397.40  5301.8 1398.26  5366.5 1397.45  5387.4 1398.29
  5451.0 1397.06  5514.7 1397.59  5798.9 1402.02  5827.4 1403.62  5841.5 1403.05
  5919.6 1405.19  5926.2 1404.37  5997.5 1405.60  6153.3 1411.66  6316.3 1421.53
#Mann=3,-1,0
  4047.2    0.05       0  4993.9    0.05       0  4999.3    0.05       0
Bank Sta=4993.9,4999.3
Exp/Cntr=0.3,0.1

Type RM Length L Ch R = 1,7500,500,500,500
BEGIN DESCRIPTION:
SANFERNANDO032 15.0
END DESCRIPTION:
XS GIS Cut Line= 3
      2777355.70     10288803.07      2777598.81     10288012.50
      2777805.69     10287003.08
#Sta/Elev= 30
  4172.9 1410.26  4277.5 1406.26  4292.5 1406.35  4382.1 1401.96  4428.6 1400.95
  4539.0 1396.15  4612.3 1394.68  4706.4 1390.39  4798.8 1388.52  4907.4 1387.66
  4934.9 1385.58  4940.1 1386.41  4964.9 1384.68  4965.3 1384.18  4970.3 1384.68
  5006.9 1384.77  5081.0 1390.69  5112.9 1392.35  5193.3 1393.78  5387.3 1394.58
  5489.4 1396.49  5499.6 1396.56  5506.0 1395.61  5511.1 1396.53  5632.3 1399.16
  5734.3 1403.00  5853.9 1406.44  5887.5 1406.33  5904.3 1407.81  6030.4 1411.06
#Mann=3,-1,0
  4172.9    0.05       0  4964.9    0.05       0  4970.3    0.05       0
Bank Sta=4964.9,4970.3
Exp/Cntr=0.3,0.1