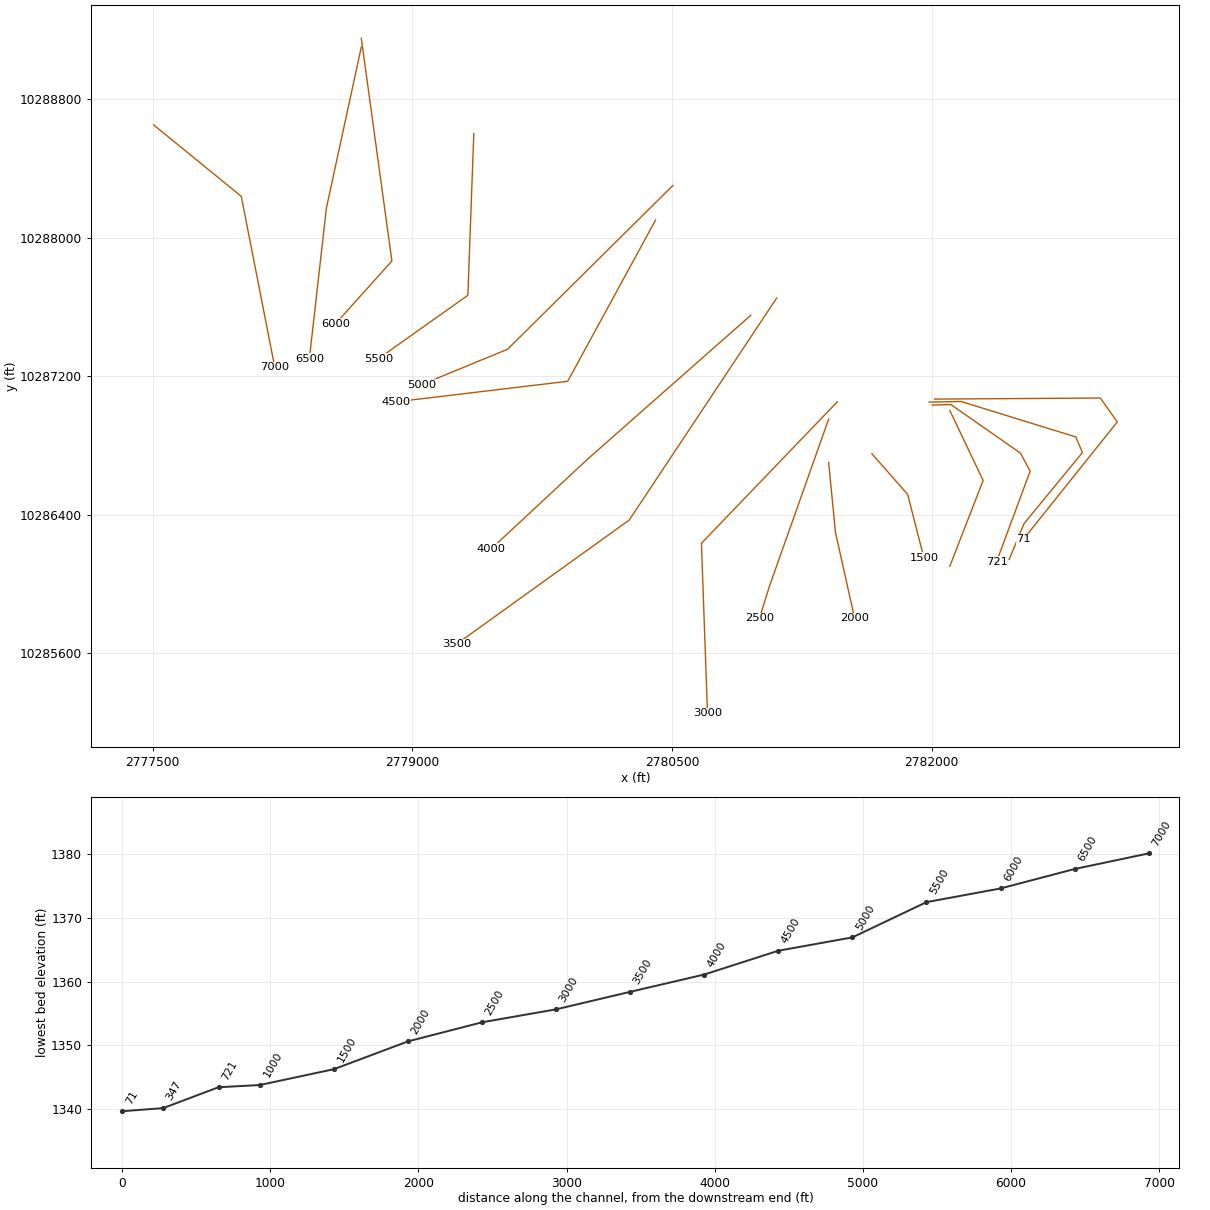
HEC-RAS study SANFERNANDO032.prj: SANFERNANDO032 Base Level Engineering

--- SANFERNANDO032.g01 (geometry) --- (continued)

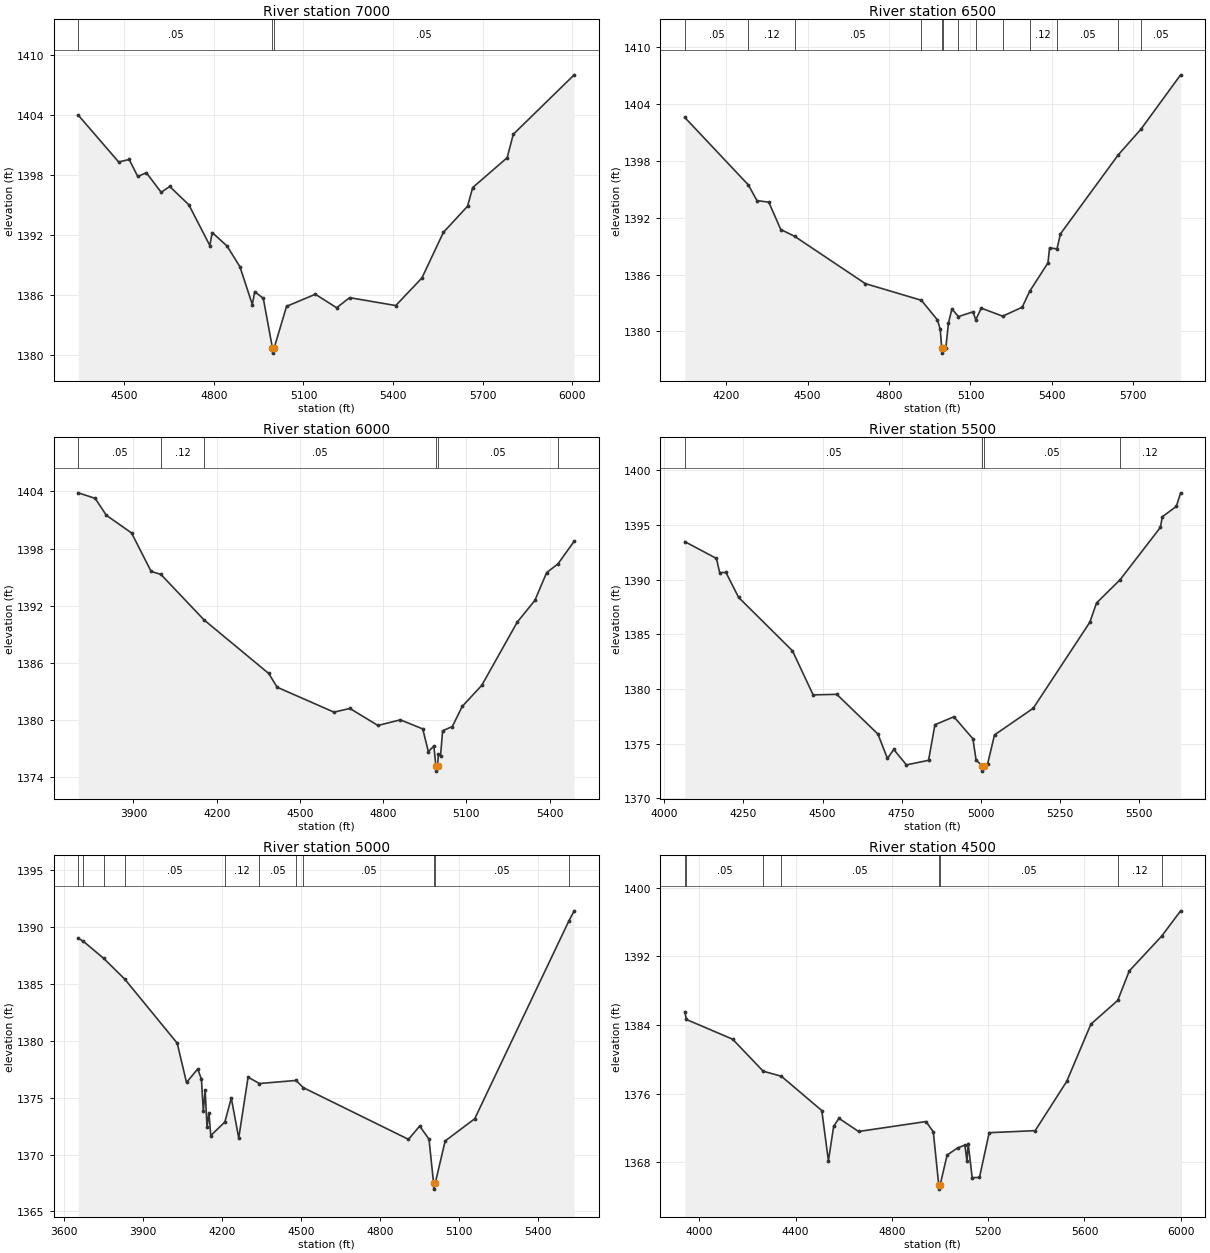
Type RM Length L Ch R = 1,7000,500,500,500
BEGIN DESCRIPTION:
SANFERNANDO032 14.0
END DESCRIPTION:
XS GIS Cut Line= 3
      2777505.70     10288653.10      2778012.25     10288240.23
      2778205.69     10287253.10
#Sta/Elev= 30
  4346.5 1403.96  4481.5 1399.28  4516.7 1399.53  4545.4 1397.83  4574.1 1398.21
  4623.7 1396.25  4652.4 1396.83  4716.3 1395.00  4786.7 1390.92  4794.6 1392.22
  4844.1 1390.88  4887.2 1388.81  4928.8 1385.02  4936.8 1386.31  4965.5 1385.64
  4996.2 1380.66  4996.7 1380.16  5001.7 1380.66  5043.4 1384.84  5139.7 1386.05
  5211.1 1384.70  5254.4 1385.71  5408.8 1384.92  5496.4 1387.68  5568.3 1392.24
  5649.2 1394.86  5666.2 1396.72  5781.7 1399.71  5802.1 1402.05  6005.9 1408.00
#Mann=3,-1,0
  4346.5    0.05       0  4996.2    0.05       0  5001.7    0.05       0
Bank Sta=4996.2,5001.7
Exp/Cntr=0.3,0.1

Type RM Length L Ch R = 1,6500,500,500,500
BEGIN DESCRIPTION:
SANFERNANDO032 13.0
END DESCRIPTION:
XS GIS Cut Line= 3
      2778705.68     10289103.10      2778503.94     10288172.00
      2778405.69     10287303.14
#Sta/Elev= 30
  4047.3 1402.59  4281.4 1395.47  4313.3 1393.81  4356.8 1393.65  4400.9 1390.76
  4451.6 1390.05  4712.4 1385.05  4919.0 1383.29  4978.4 1381.21  4988.6 1380.22
  4994.1 1378.21  4994.5 1377.71  4999.7 1378.21  5008.9 1378.22  5019.0 1380.89
  5031.5 1382.38  5055.7 1381.57  5109.6 1382.07  5119.4 1381.23  5139.8 1382.46
  5218.7 1381.61  5290.7 1382.56  5318.0 1384.23  5385.6 1387.24  5391.4 1388.81
  5418.8 1388.72  5431.6 1390.30  5644.7 1398.65  5727.7 1401.33  5874.4 1407.09
#Mann=13,-1,0
  4047.3    0.05       0  4281.4    0.12       0  4451.6    0.05       0
  4919.0    0.12       0  4994.1    0.07       0  4999.7    0.12       0
  5055.7    0.05       0  5119.4    0.12       0  5218.7    0.05       0
  5318.0    0.12       0  5418.8    0.05       0  5644.7    0.12       0
  5727.7    0.05       0
Bank Sta=4994.1,4999.7
Exp/Cntr=0.3,0.1

Type RM Length L Ch R = 1,6000,500,500,500
BEGIN DESCRIPTION:
SANFERNANDO032 12.0
END DESCRIPTION:
XS GIS Cut Line= 3
      2778705.68     10289153.11      2778882.36     10287866.49
      2778555.70     10287503.13
#Sta/Elev= 30
  3701.3 1403.84  3761.9 1403.26  3802.2 1401.49  3893.1 1399.63  3963.7 1395.60
  3999.0 1395.28  4154.5 1390.51  4387.7 1384.89  4418.0 1383.45  4622.5 1380.84
  4680.4 1381.22  4781.3 1379.44  4862.1 1380.03  4942.8 1379.08  4963.0 1376.70
  4982.9 1377.28  4990.4 1375.15  4990.9 1374.65  4996.2 1375.15  4999.2 1376.42
  5006.9 1376.24  5014.4 1378.88  5049.5 1379.33  5085.2 1381.44  5155.6 1383.65
  5283.5 1390.28  5347.0 1392.56  5389.6 1395.48  5429.8 1396.37  5488.6 1398.76
#Mann=6,-1,0
  3701.3    0.05       0  3999.0    0.12       0  4154.5    0.05       0
  4990.4    0.05       0  4996.2    0.05       0  5429.8    0.12       0
Bank Sta=4990.4,4996.2
Exp/Cntr=0.3,0.1

Type RM Length L Ch R = 1,5500,500,500,500
BEGIN DESCRIPTION:
SANFERNANDO032 11.0
END DESCRIPTION:
XS GIS Cut Line= 3
      2779355.69     10288603.13      2779321.14     10287668.37
      2778805.64     10287303.08
#Sta/Elev= 30
  4064.6 1393.48  4164.7 1391.94  4174.7 1390.65  4194.7 1390.66  4234.7 1388.38
  4404.9 1383.50  4470.3 1379.47  4545.0 1379.52  4675.0 1375.89  4705.1 1373.66
  4725.1 1374.48  4765.1 1373.07  4835.1 1373.49  4855.2 1376.74  4915.2 1377.47
  4975.2 1375.46  4985.3 1373.52  5003.8 1373.00  5004.2 1372.50  5009.6 1373.00
  5021.4 1373.12  5043.5 1375.81  5166.0 1378.25  5345.0 1386.12  5366.0 1387.87
  5440.5 1390.00  5567.8 1394.78  5573.9 1395.75  5618.2 1396.70  5631.8 1397.94
#Mann=4,-1,0
  4064.6    0.05       0  5003.8    0.05       0  5009.6    0.05       0
  5440.5    0.12       0
Bank Sta=5003.8,5009.6
Exp/Cntr=0.3,0.1

Type RM Length L Ch R = 1,5000,500,500,500
BEGIN DESCRIPTION:
SANFERNANDO032 10.0
END DESCRIPTION:
XS GIS Cut Line= 3
      2780505.69     10288303.12      2779550.97     10287357.02
      2779055.70     10287153.12
#Sta/Elev= 30
  3655.9 1389.01  3673.3 1388.79  3751.9 1387.26  3831.6 1385.44  4030.7 1379.80
  4066.0 1376.34  4108.4 1377.53  4122.6 1376.63  4129.7 1373.81  4136.7 1375.67
  4143.8 1372.43  4150.9 1373.69  4158.0 1371.67  4211.5 1372.87  4235.7 1374.98
  4264.0 1371.46  4299.4 1376.81  4342.3 1376.25  4481.4 1376.52  4508.6 1375.89
  4907.5 1371.34  4950.0 1372.51  4985.3 1371.35  5002.8 1367.46  5003.3 1366.96
  5008.7 1367.46  5046.6 1371.20  5158.6 1373.15  5515.3 1390.54  5535.6 1391.44
#Mann=11,-1,0
  3655.9    0.12       0  3673.3    0.05       0  3751.9    0.12       0
  3831.6    0.05       0  4211.5    0.12       0  4342.3    0.05       0
  4481.4    0.12       0  4508.6    0.05       0  5002.8    0.05       0
  5008.7    0.05       0  5515.3    0.12       0
Bank Sta=5002.8,5008.7
Exp/Cntr=0.3,0.1

Type RM Length L Ch R = 1,4500,500,500,500
BEGIN DESCRIPTION:
SANFERNANDO032 9.0
END DESCRIPTION:
XS GIS Cut Line= 3
      2780405.66     10288103.08      2779898.13     10287171.79
      2778905.71     10287053.11
#Sta/Elev= 30
  3939.4 1385.55  3946.1 1384.64  4138.3 1382.34  4265.1 1378.61  4340.8 1378.02
  4508.6 1374.02  4536.1 1368.17  4557.9 1372.18  4579.8 1373.12  4661.4 1371.58
  4941.6 1372.74  4971.9 1371.54  4994.4 1365.36  4994.9 1364.86  5000.3 1365.36
  5029.3 1368.83  5073.0 1369.67  5103.2 1369.99  5111.7 1368.11  5116.8 1370.18
  5133.4 1366.20  5163.6 1366.22  5204.2 1371.44  5395.2 1371.68  5526.2 1377.42
  5626.9 1384.11  5738.1 1386.86  5786.0 1390.30  5920.5 1394.35  5999.5 1397.31
#Mann=8,-1,0
  3939.4    0.12       0  3946.1    0.05       0  4265.1    0.12       0
  4340.8    0.05       0  4994.4    0.05       0  5000.3    0.05       0
  5738.1    0.12       0  5920.5    0.05       0
Bank Sta=4994.4,5000.3
Exp/Cntr=0.3,0.1

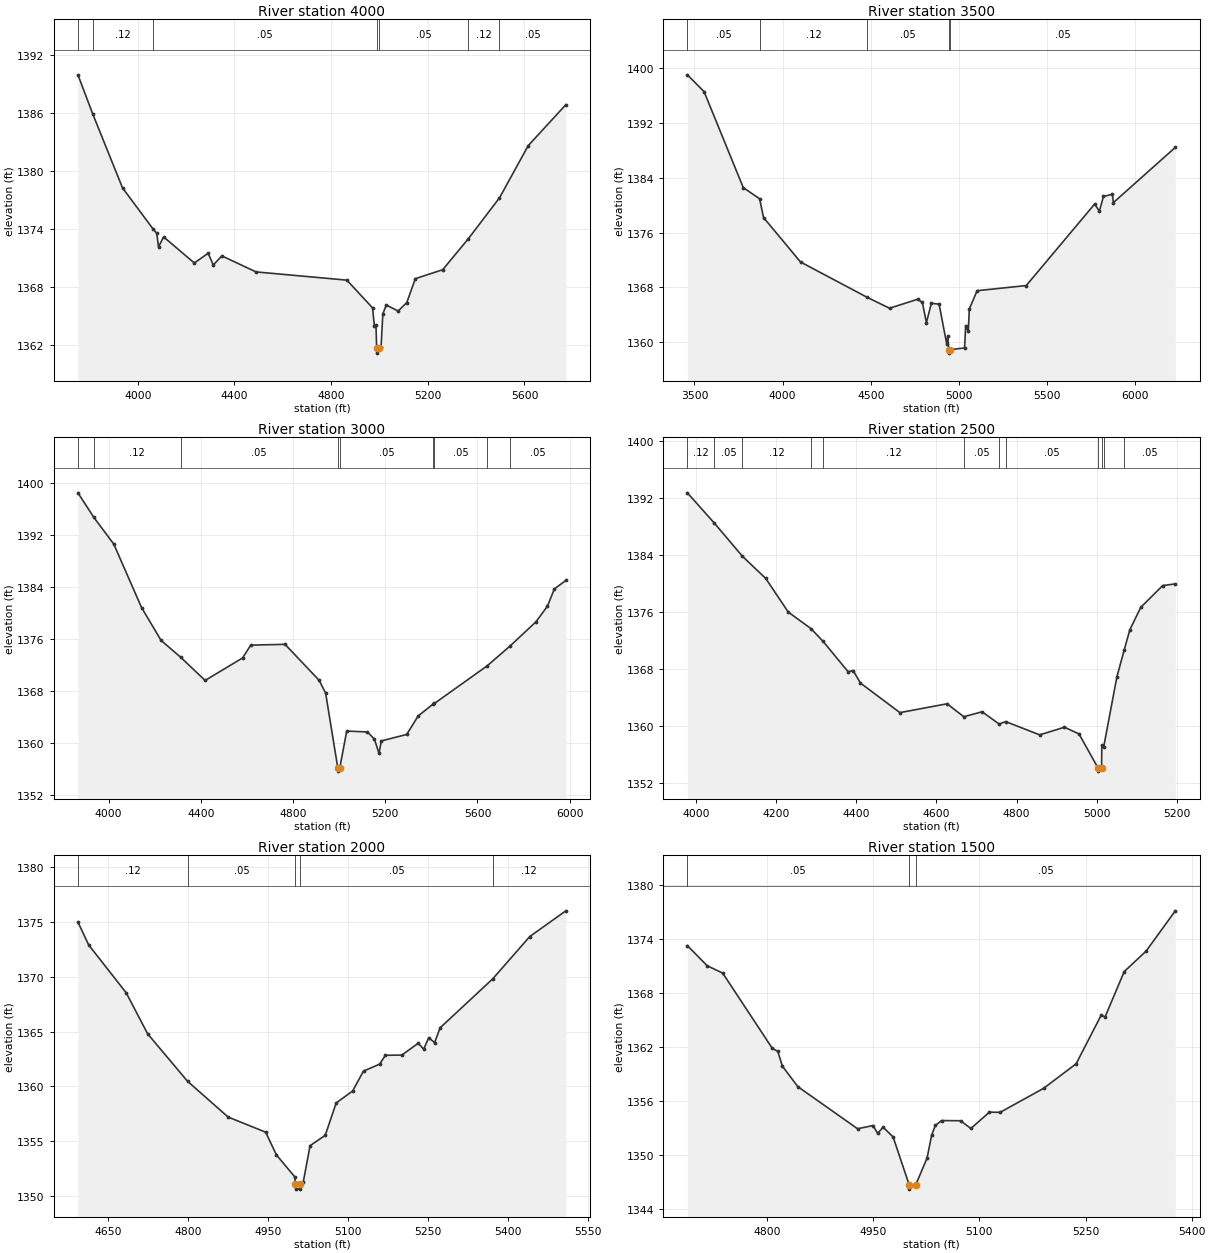
Type RM Length L Ch R = 1,4000,500,500,500
BEGIN DESCRIPTION:
SANFERNANDO032 8.0
END DESCRIPTION:
XS GIS Cut Line= 3
      2780955.72     10287553.14      2780020.21     10286728.32
      2779455.66     10286203.09
#Sta/Elev= 30
  3752.8 1389.94  3814.0 1385.89  3937.3 1378.23  4063.4 1373.98  4078.7 1373.54
  4086.1 1372.12  4107.2 1373.16  4234.3 1370.45  4291.2 1371.46  4312.8 1370.25
  4348.1 1371.19  4489.5 1369.53  4865.1 1368.68  4971.4 1365.81  4979.0 1363.95
  4985.6 1364.05  4988.5 1361.62  4989.0 1361.12  4997.0 1361.62  5006.7 1361.78
  5014.0 1365.18  5028.2 1366.10  5077.5 1365.48  5113.2 1366.36  5148.4 1368.83
  5261.7 1369.76  5366.8 1372.94  5496.5 1377.20  5615.5 1382.61  5771.1 1386.85
#Mann=7,-1,0
  3752.8    0.05       0  3814.0    0.12       0  4063.4    0.05       0
  4988.5    0.05       0  4997.0    0.05       0  5366.8    0.12       0
  5496.5    0.05       0
Bank Sta=4988.5,4997
Exp/Cntr=0.3,0.1

Type RM Length L Ch R = 1,3500,500,500,500
BEGIN DESCRIPTION:
SANFERNANDO032 7.0
END DESCRIPTION:
XS GIS Cut Line= 3
      2781105.68     10287653.10      2780253.54     10286369.99
      2779255.66     10285653.09
#Sta/Elev= 30
  3459.7 1399.01  3554.4 1396.56  3776.9 1382.55  3869.7 1380.92  3891.8 1378.19
  4101.7 1371.70  4481.0 1366.53  4606.8 1364.95  4766.2 1366.26  4793.2 1365.80
  4816.2 1362.84  4844.3 1365.68  4888.2 1365.54  4931.5 1359.73  4937.5 1360.89
  4942.3 1358.90  4942.8 1358.40  4950.9 1358.90  5032.8 1359.16  5039.0 1362.42
  5053.7 1361.59  5059.9 1364.86  5104.0 1367.51  5382.8 1368.26  5770.7 1380.15
  5797.7 1379.12  5821.0 1381.26  5871.4 1381.58  5877.5 1380.37  6228.7 1388.42
#Mann=5,-1,0
  3459.7    0.05       0  3869.7    0.12       0  4481.0    0.05       0
  4942.3    0.05       0  4950.9    0.05       0
Bank Sta=4942.3,4950.9
Exp/Cntr=0.3,0.1

Type RM Length L Ch R = 1,3000,500,500,500
BEGIN DESCRIPTION:
SANFERNANDO032 6.0
END DESCRIPTION:
XS GIS Cut Line= 3
      2781455.68     10287053.10      2780670.74     10286235.78
      2780705.68     10285253.10
#Sta/Elev= 30
  3866.8 1398.43  3935.3 1394.68  4022.3 1390.55  4142.7 1380.80  4227.3 1375.75
  4311.7 1373.18  4418.5 1369.59  4581.1 1373.05  4616.4 1375.02  4765.1 1375.14
  4913.5 1369.59  4941.3 1367.63  4994.0 1356.15  4994.5 1355.65  5002.7 1356.15
  5032.7 1361.81  5122.7 1361.67  5152.8 1360.57  5172.8 1358.39  5182.8 1360.29
  5292.9 1361.29  5342.9 1364.14  5406.5 1365.93  5413.4 1366.06  5641.8 1371.83
  5739.9 1374.84  5853.2 1378.59  5903.2 1380.99  5933.3 1383.65  5983.3 1384.97
#Mann=9,-1,0
  3866.8    0.05       0  3935.3    0.12       0  4311.7    0.05       0
  4994.0    0.05       0  5002.7    0.05       0  5406.5    0.12       0
  5413.4    0.05       0  5641.8    0.12       0  5739.9    0.05       0
Bank Sta=4994,5002.7
Exp/Cntr=0.3,0.1

Type RM Length L Ch R = 1,2500,500,500,500
BEGIN DESCRIPTION:
SANFERNANDO032 5.0
END DESCRIPTION:
XS GIS Cut Line= 3
      2781405.68     10286953.10      2781064.59     10285990.23
      2781005.68     10285803.08
#Sta/Elev= 30
  3978.5 1392.66  4046.0 1388.40  4115.8 1383.76  4173.9 1380.66  4230.4 1375.92
  4287.0 1373.61  4317.3 1371.81  4379.6 1367.56  4392.2 1367.72  4410.4 1365.97
  4508.9 1361.82  4626.6 1363.06  4668.4 1361.24  4714.0 1361.94  4756.5 1360.22
  4772.8 1360.56  4857.8 1358.70  4919.6 1359.77  4955.8 1358.83  5002.8 1354.11
  5003.3 1353.61  5012.1 1354.11  5012.8 1357.31  5017.2 1356.93  5050.5 1366.86
  5068.5 1370.57  5082.8 1373.46  5110.0 1376.59  5164.7 1379.65  5196.2 1379.88
#Mann=12,-1,0
  3978.5    0.12       0  4046.0    0.05       0  4115.8    0.12       0
  4287.0    0.05       0  4317.3    0.12       0  4668.4    0.05       0
  4756.5    0.12       0  4772.8    0.05       0  5002.8    0.05       0
  5012.1    0.05       0  5017.2    0.12       0  5068.5    0.05       0
Bank Sta=5002.8,5012.1
Exp/Cntr=0.3,0.1

Type RM Length L Ch R = 1,2000,500,500,500
BEGIN DESCRIPTION:
SANFERNANDO032 4.0
END DESCRIPTION:
XS GIS Cut Line= 3
      2781405.68     10286703.15      2781444.99     10286299.15
      2781555.67     10285803.15
#Sta/Elev= 30
  4594.1 1374.99  4614.2 1372.91  4684.6 1368.53  4724.7 1364.79  4799.4 1360.46
  4875.5 1357.19  4945.8 1355.81  4965.9 1353.74  5000.0 1351.75  5001.5 1351.11
  5002.0 1350.61  5010.4 1350.61  5010.9 1351.11  5016.4 1351.30  5029.0 1354.58
  5057.4 1355.52  5077.9 1358.48  5108.7 1359.57  5129.1 1361.39  5159.3 1362.02
  5170.1 1362.83  5200.9 1362.85  5231.6 1363.93  5241.8 1363.39  5251.3 1364.43
  5262.3 1363.99  5272.6 1365.34  5371.2 1369.81  5440.5 1373.67  5508.2 1376.02
#Mann=5,-1,0
  4594.1    0.12       0  4799.4    0.05       0  5001.5    0.05       0
  5010.9    0.05       0  5371.2    0.12       0
Bank Sta=5001.5,5010.9
Exp/Cntr=0.3,0.1

Type RM Length L Ch R = 1,1500,500,500,500
BEGIN DESCRIPTION:
SANFERNANDO032 3.0
END DESCRIPTION:
XS GIS Cut Line= 3
      2781655.65     10286753.15      2781862.24     10286518.27
      2781955.68     10286153.14
#Sta/Elev= 30
  4687.2 1373.30  4715.3 1371.06  4737.1 1370.25  4807.3 1361.88  4814.9 1361.56
  4821.5 1359.91  4843.3 1357.63  4927.8 1352.95  4949.6 1353.31  4956.2 1352.43
  4963.8 1353.13  4978.0 1352.04  5000.6 1346.74  5001.1 1346.24  5010.1 1346.74
  5026.0 1349.69  5032.6 1352.28  5037.8 1353.32  5046.6 1353.86  5073.4 1353.84
  5087.9 1352.98  5114.2 1354.80  5129.2 1354.77  5190.7 1357.44  5236.7 1360.17
  5272.3 1365.60  5277.5 1365.36  5304.7 1370.42  5335.6 1372.69  5376.9 1377.17
#Mann=3,-1,0
  4687.2    0.05       0  5000.6    0.05       0  5010.1    0.05       0
Bank Sta=5000.6,5010.1
Exp/Cntr=0.3,0.1

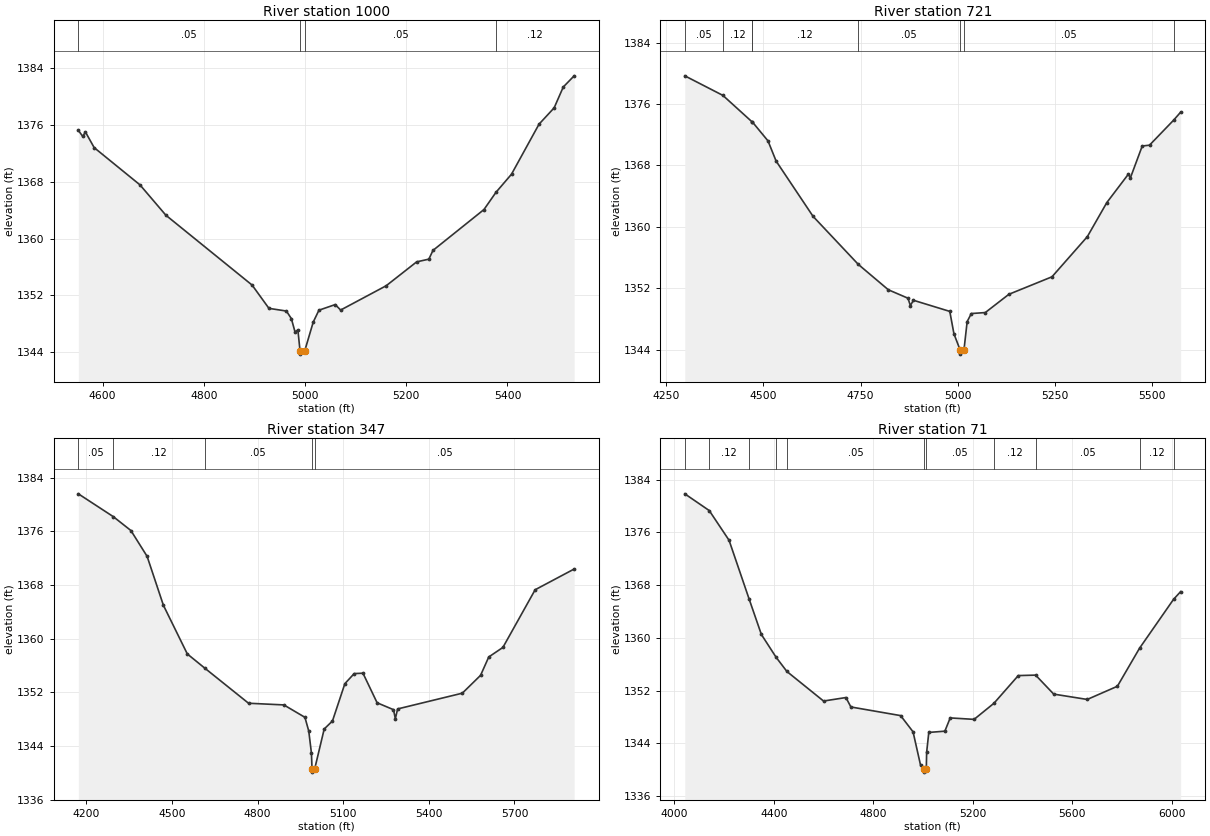
Type RM Length L Ch R = 1,1000,279,279,279
BEGIN DESCRIPTION:
SANFERNANDO032 2.0
END DESCRIPTION:
XS GIS Cut Line= 3
      2782105.68     10287003.11      2782298.34     10286598.76
      2782105.68     10286103.09
#Sta/Elev= 30
  4552.1 1375.23  4560.7 1374.39  4566.2 1374.99  4583.4 1372.80  4673.9 1367.56
  4725.1 1363.29  4895.5 1353.46  4928.7 1350.19  4963.2 1349.81  4973.0 1348.75
  4980.4 1346.84  4985.9 1347.17  4990.1 1344.25  4990.6 1343.75  4999.6 1344.25
  5016.3 1348.27  5027.5 1349.93  5059.7 1350.72  5070.4 1349.95  5160.4 1353.37
  5220.6 1356.73  5244.7 1357.11  5252.8 1358.34  5353.6 1364.09  5377.4 1366.52
  5408.0 1369.06  5462.4 1376.10  5492.3 1378.40  5510.3 1381.33  5531.8 1382.90
#Mann=4,-1,0
  4552.1    0.05       0  4990.1    0.05       0  4999.6    0.05       0
  5377.4    0.12       0
Bank Sta=4990.1,4999.6
Exp/Cntr=0.3,0.1

Type RM Length L Ch R = 1,721,374,374,374
BEGIN DESCRIPTION:
Mapping XS 5909130b
END DESCRIPTION:
XS GIS Cut Line= 5
      2782003.80     10287034.15      2782111.47     10287037.62
      2782514.25     10286756.37      2782569.80     10286652.21
      2782375.41     10286128.03
#Sta/Elev= 30
  4297.5 1379.68  4395.5 1377.13  4470.6 1373.68  4471.2 1373.68  4511.6 1371.20
  4532.5 1368.57  4627.6 1361.36  4744.2 1355.09  4821.3 1351.79  4871.9 1350.69
  4878.0 1349.73  4886.0 1350.42  4979.5 1348.97  4990.2 1346.05  5006.4 1343.90
  5006.9 1343.40  5015.9 1343.90  5024.2 1347.64  5034.9 1348.69  5070.9 1348.82
  5131.6 1351.20  5242.5 1353.48  5333.6 1358.72  5383.7 1363.16  5439.1 1366.86
  5444.5 1366.40  5474.8 1370.53  5493.5 1370.64  5555.4 1373.89  5573.6 1374.94
#Mann=8,-1,0
  4297.5    0.05       0  4395.5    0.12       0  4470.6    0.05       0
  4471.2    0.12       0  4744.2    0.05       0  5006.4    0.05       0
  5015.9    0.05       0  5555.4    0.12       0
Bank Sta=5006.4,5015.9
Exp/Cntr=0.3,0.1

Type RM Length L Ch R = 1,347,276,276,276
BEGIN DESCRIPTION:
Mapping XS 13fc8f01
END DESCRIPTION:
XS GIS Cut Line= 6
      2781986.45     10287051.51      2782170.50     10287054.98
      2782833.69     10286850.12      2782871.89     10286759.84
      2782535.08     10286350.12      2782448.28     10286141.79
#Sta/Elev= 30
  4172.3 1381.61  4295.0 1378.20  4356.4 1376.14  4413.2 1372.29  4470.3 1364.99
  4554.0 1357.74  4614.4 1355.65  4768.5 1350.39  4892.2 1350.14  4966.0 1348.29
  4979.4 1346.24  4988.8 1342.94  4990.8 1340.62  4991.3 1340.12  5000.3 1340.62
  5033.5 1346.55  5062.5 1347.75  5105.9 1353.31  5138.5 1354.81  5169.3 1354.87
  5218.8 1350.46  5276.2 1349.43  5282.7 1348.08  5290.6 1349.54  5517.3 1351.89
  5581.2 1354.55  5609.9 1357.29  5659.4 1358.71  5772.4 1367.31  5909.0 1370.40
#Mann=5,-1,0
  4172.3    0.05       0  4295.0    0.12       0  4614.4    0.05       0
  4990.8    0.05       0  5000.3    0.05       0
Bank Sta=4990.8,5000.3
Exp/Cntr=0.3,0.1

Type RM Length L Ch R = 1,71,0,0,0
BEGIN DESCRIPTION:
Mapping XS b1babf3b
END DESCRIPTION:
XS GIS Cut Line= 4
      2782017.72     10287068.87      2782975.50     10287075.00
      2783073.28     10286936.93      2782531.59     10286259.83
#Sta/Elev= 30
  4042.2 1381.83  4140.6 1379.29  4220.2 1374.79  4300.4 1365.93  4350.2 1360.50
  4409.5 1357.04  4452.9 1354.89  4600.2 1350.41  4690.2 1350.94  4710.2 1349.51
  4910.2 1348.20  4960.2 1345.74  4990.2 1340.71  5003.9 1340.13  5004.4 1339.63
  5013.5 1340.13  5014.8 1342.61  5023.5 1345.65  5088.1 1345.84  5109.6 1347.85
  5205.7 1347.63  5285.5 1350.07  5383.4 1354.27  5453.1 1354.34  5525.9 1351.46
  5660.7 1350.65  5782.0 1352.65  5871.1 1358.42  6008.0 1365.84  6036.3 1367.00
#Mann=11,-1,0
  4042.2    0.05       0  4140.6    0.12       0  4300.4    0.05       0
  4409.5    0.12       0  4452.9    0.05       0  5003.9    0.05       0
  5013.5    0.05       0  5285.5    0.12       0  5453.1    0.05       0
  5871.1    0.12       0  6008.0    0.05       0
Bank Sta=5003.9,5013.5
Exp/Cntr=0.3,0.1

Chan Stop Cuts=-1