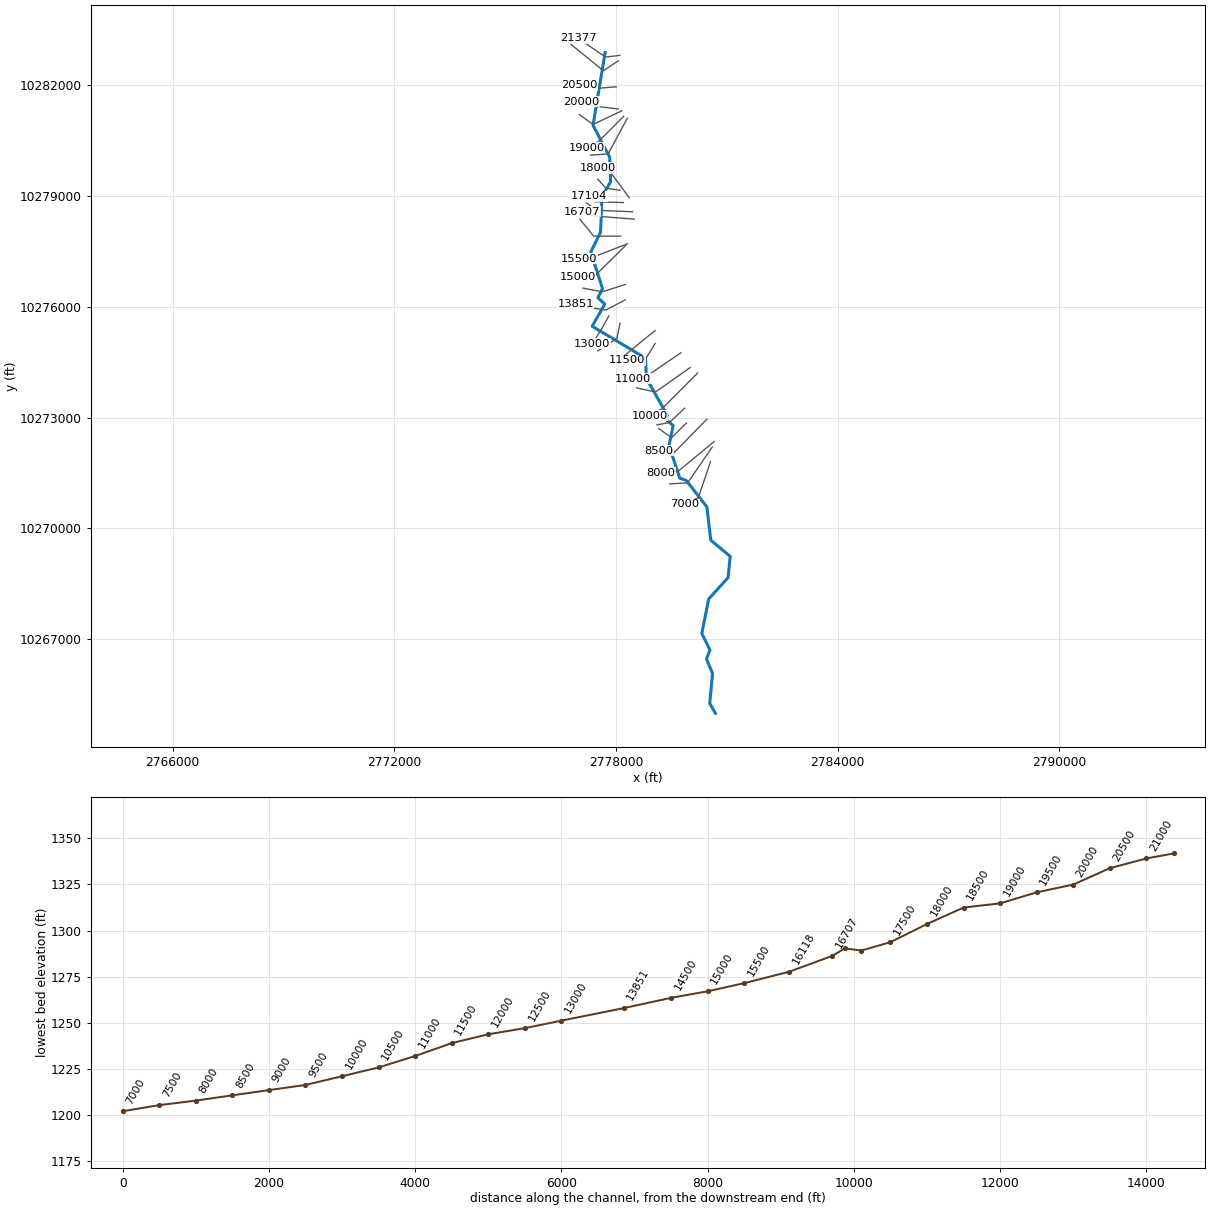
--- SANFERNANDO033.prj (project) ---

Proj Title=SANFERNANDO033 Base Level Engineering
Current Plan=p01
Default Exp/Contr=0.3,0.1
English Units
Geom File=g01
Flow File=f01
Plan File=p01
Y Axis Title=Elevation
X Axis Title(PF)=Main Channel Distance
X Axis Title(XS)=Station
BEGIN DESCRIPTION:
SANFERNANDO033
END DESCRIPTION:
DSS Export Rating Curves= 0
DSS Export Rating Curve Sorted= 0
DSS Export Volume Flow Curves= 0
DXF OffsetX= 0
DXF OffsetY= 0
DXF ScaleX= 1
DXF ScaleY= 10

--- SANFERNANDO033.p01 (plan) ---

Plan Title=Multiple Run
Short Identifier=Multiple
Geom File=g01
Flow File=f01
Subcritical Flow
K Sum by GR= 0
Std Step Tol= 0.01
Critical Tol= 0.01
Num of Std Step Trials= 20
Max Error Tol= 0.3
Flow Tol Ratio= 0.001
Split Flow NTrial= 30
Split Flow Tol= 0.02
Split Flow Ratio= 0.02
Log Output Level= 0
Friction Slope Method= 1
Unsteady Friction Slope Method= 2
Unsteady Bridges Friction Slope Method= 1
Parabolic Critical Depth
Global Vel Dist=  1 , 1 , 1
Global Log Level= 0
CheckData=True
Encroach Param= -1, 0, 0, 0
BEGIN DESCRIPTION:
Multiple Run
END DESCRIPTION:

--- SANFERNANDO033.f01 (steady flow) ---

Flow Title=Multiple
Number of Profiles=7
Profile Names=10-year,25-year,50-year,1pct_min,100-year,1pct_plu,500-year
River Rch & RM= SANFERNANDO033,Reach-1,21377
     415     669     953     562    1276    2896    1762
River Rch & RM= SANFERNANDO033,Reach-1,15500
     780    1321    1772    1172    2417    4983    3337
River Rch & RM= SANFERNANDO033,Reach-1,5000
     996    1711    2375    1475    3268    7240    4499
River Rch & RM= SANFERNANDO033,Reach-1,2000
    1707    2998    4953    3324    6991   14703    9573
Boundary for River Rch & Prof#=SANFERNANDO033,Reach-1,1
Up Type=0
Dn Type=3
Dn Slope=0.005
Boundary for River Rch & Prof#=SANFERNANDO033,Reach-1,2
Up Type=0
Dn Type=3
Dn Slope=0.005
Boundary for River Rch & Prof#=SANFERNANDO033,Reach-1,3
Up Type=0
Dn Type=3
Dn Slope=0.005
Boundary for River Rch & Prof#=SANFERNANDO033,Reach-1,4
Up Type=0
Dn Type=3
Dn Slope=0.005
Boundary for River Rch & Prof#=SANFERNANDO033,Reach-1,5
Up Type=0
Dn Type=3
Dn Slope=0.005
Boundary for River Rch & Prof#=SANFERNANDO033,Reach-1,6
Up Type=0
Dn Type=3
Dn Slope=0.005
Boundary for River Rch & Prof#=SANFERNANDO033,Reach-1,7
Up Type=0
Dn Type=3
Dn Slope=0.005

--- SANFERNANDO033.g01 (geometry) ---

Geom Title=Existing Conditions
Program Version=4.10

River Reach=SANFERNANDO033  ,Reach-1
Reach XY= 30
       2777703.5       10282881.      2777376.25       10280912.
      2777828.25       10280046.      2777853.25       10279386.
      2777618.75       10278980.      2777580.25       10278020.
      2777316.25       10277478.      2777632.75       10276490.
        2777508.       10276242.       2777694.5       10276072.
      2777353.75       10275471.      2778798.75       10274607.
       2778819.5       10274065.      2779389.75       10273058.
        2779341.       10272960.        2779545.       10272782.
      2779432.25       10272241.      2779724.75       10271361.
       2779903.5       10271295.       2780457.5       10270580.
      2780564.25       10269681.      2781089.25       10269242.
      2781031.25       10268667.        2780507.       10268091.
      2780320.25       10267155.      2780540.75       10266712.
      2780447.75       10266463.        2780612.       10266075.
       2780535.5       10265265.      2780689.75       10264993.

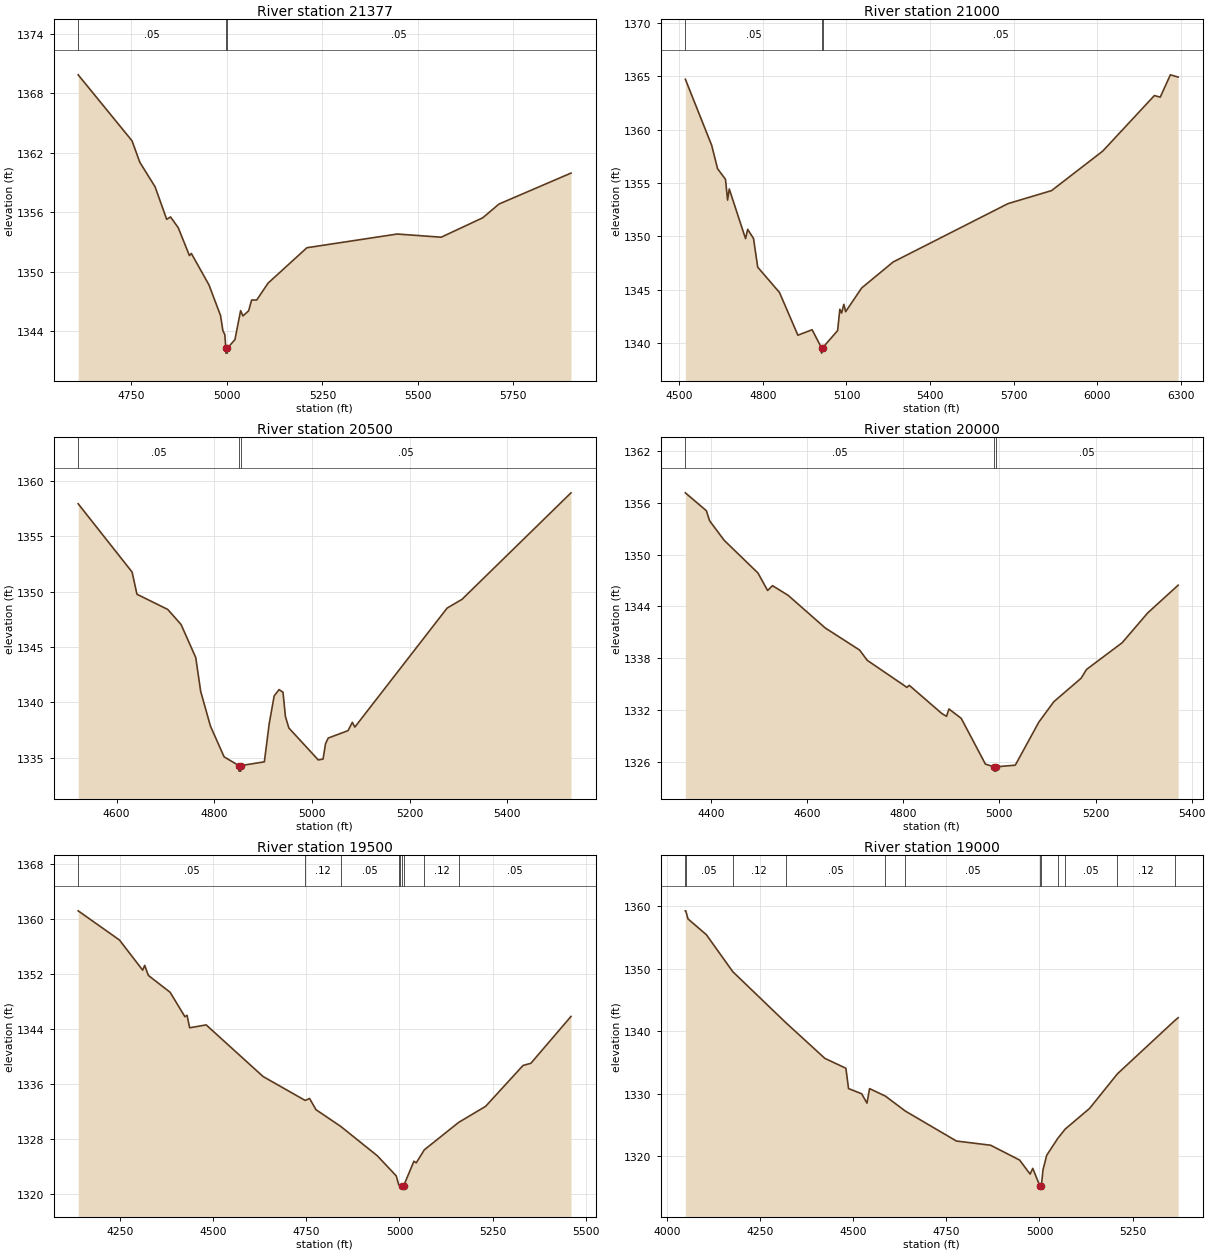
Type RM Length L Ch R = 1 ,21377   ,377,377,377
BEGIN DESCRIPTION:
SANFERNANDO033 43.0
END DESCRIPTION:
XS GIS Cut Line= 3
      2778105.71     10282803.11      2777719.25       10282757.
      2776974.98     10283264.28
#Sta/Elev= 30
  4610.8 1369.84  4751.8 1363.19    4772 1361.04  4812.2 1358.55  4842.5 1355.28
  4852.5 1355.52  4872.7 1354.44    4902 1351.63  4907.1 1351.84  4953.2 1348.67
  4983.4 1345.59  4989.6 1344.06  4994.6 1343.67  4997.3  1342.3  4997.5  1341.8
    5001  1341.8  5001.3  1342.3  5021.1 1343.16    5036 1346.08  5042.1 1345.55
    5057 1346.07  5064.8 1347.15    5078 1347.15  5107.8 1348.85  5209.5 1352.42
  5445.9  1353.8    5561 1353.48  5669.9 1355.44  5712.2 1356.82  5900.7 1359.94
#Mann= 3 ,-1 , 0
  4610.8     .05       0  4997.3     .05       0  5001.3     .05       0
Bank Sta=4997.3,5001.3
XS Rating Curve= 0 ,0
Exp/Cntr=0.3,0.1

Type RM Length L Ch R = 1 ,21000   ,500,500,500
BEGIN DESCRIPTION:
SANFERNANDO033 42.0
END DESCRIPTION:
XS GIS Cut Line= 3
      2778055.65     10282653.09      2777657.25     10282387.87
       2776655.7      10283203.1
#Sta/Elev= 30
  4521.4 1364.72    4616 1358.53  4637.1 1356.34  4665.5 1355.35  4673.1  1353.4
  4679.1 1354.44  4737.6 1349.79  4745.3 1350.66  4766.3  1349.8  4781.3 1347.12
  4859.5 1344.75  4925.6 1340.75  4976.7 1341.26  5010.4 1339.57  5010.6 1339.07
  5014.4 1339.57  5068.3 1341.18  5076.3 1343.18  5082.7 1342.82  5090.6 1343.64
  5097.1 1342.95  5154.6 1345.17    5268 1347.61  5680.3 1353.07  5836.8 1354.29
  6020.6 1357.99    6206 1363.19    6227 1363.04  6263.4 1365.13  6291.4 1364.92
#Mann= 3 ,-1 , 0
  4521.4     .05       0  5010.4     .03       0  5014.4     .05       0
Bank Sta=5010.4,5014.4
XS Rating Curve= 0 ,0
Exp/Cntr=0.3,0.1

Type RM Length L Ch R = 1 ,20500   ,500,500,500
BEGIN DESCRIPTION:
SANFERNANDO033 41.0
END DESCRIPTION:
XS GIS Cut Line= 3
      2778005.69     10281953.11      2777528.73     10281913.47
      2777005.66     10282003.12
#Sta/Elev= 30
  4521.4 1357.95  4631.8 1351.78  4641.8 1349.77  4704.8  1348.4  4732.1 1347.04
  4762.2 1344.05  4772.3 1340.99  4792.3 1337.85  4820.3 1335.07  4850.5 1334.28
  4850.8 1333.78  4854.3 1333.78  4854.5 1334.28  4902.7 1334.62  4912.7 1338.09
  4922.8 1340.58  4932.8 1341.15  4940.9 1340.91  4945.9 1338.71  4952.9 1337.68
  5013.2 1334.79  5022.9 1334.87    5028 1336.26  5033.5 1336.77  5074.1 1337.44
  5082.9 1338.19    5088 1337.76    5277 1348.52  5307.5 1349.31  5530.7 1358.94
#Mann= 3 ,-1 , 0
  4521.4     .05       0  4850.5     .05       0  4854.5     .05       0
Bank Sta=4850.5,4854.5
XS Rating Curve= 0 ,0
Exp/Cntr=0.3,0.1

Type RM Length L Ch R = 1 ,20000   ,500,500,500
BEGIN DESCRIPTION:
SANFERNANDO033 40.0
END DESCRIPTION:
XS GIS Cut Line= 3
      2778055.68     10281353.11      2777406.89     10281430.61
      2777055.65     10281553.12
#Sta/Elev= 30
  4346.6 1357.16  4390.3 1355.09    4397 1353.93  4427.2 1351.67  4497.7 1347.87
  4517.8 1345.84  4527.9  1346.4  4560.3 1345.29  4637.7  1341.5  4709.2 1338.94
  4725.1 1337.75  4807.6 1334.62  4812.6 1334.85  4880.4 1331.58    4890 1331.26
  4895.1 1332.11  4920.6 1331.03    4971 1325.72  4989.1 1325.41  4989.4 1324.91
  4992.9 1324.91  4993.1 1325.41  5033.1  1325.6  5082.1 1330.59  5113.2 1332.95
    5170 1335.67  5181.3 1336.69  5255.5 1339.79  5308.4 1343.23    5372 1346.46
#Mann= 3 ,-1 , 0
  4346.6     .05       0  4989.1     .03       0  4993.1     .05       0
Bank Sta=4989.1,4993.1
XS Rating Curve= 0 ,0
Exp/Cntr=0.3,0.1

Type RM Length L Ch R = 1 ,19500   ,500,500,500
BEGIN DESCRIPTION:
SANFERNANDO033 39.0
END DESCRIPTION:
XS GIS Cut Line= 3
      2778155.65      10281303.1      2777377.57     10280932.12
      2777005.72     10281203.08
#Sta/Elev= 30
    4138  1361.2  4248.8 1356.95    4311 1352.57  4316.5 1353.26  4326.3  1351.8
  4384.6 1349.35  4424.4 1345.79    4430    1346  4437.1 1344.18  4481.4  1344.6
  4634.2 1337.08    4747 1333.61  4758.8 1333.89    4776 1332.26  4842.1 1329.84
  4940.4 1325.56  4991.3 1322.63    4998 1321.31  5001.3 1321.25  5007.3  1321.2
  5007.6  1320.7  5011.3  1321.2  5038.7 1324.76  5044.9 1324.52  5066.6 1326.42
  5158.7 1330.41  5231.1 1332.75  5331.5  1338.7  5352.4 1339.01  5460.1 1345.83
#Mann= 9 ,-1 , 0
    4138     .05       0    4747     .12       0  4842.1     .05       0
    4998     .12       0  5001.3     .05       0  5007.3     .07       0
  5011.3     .05       0  5066.6     .12       0  5158.7     .05       0
Bank Sta=5007.3,5011.3
XS Rating Curve= 0 ,0
Exp/Cntr=0.3,0.1

Type RM Length L Ch R = 1 ,19000   ,500,500,500
BEGIN DESCRIPTION:
SANFERNANDO033 38.0
END DESCRIPTION:
XS GIS Cut Line= 3
      2778205.67      10281153.1      2777533.97     10280479.32
      2777205.67     10280303.11
#Sta/Elev= 30
  4048.6 1359.24  4049.7 1359.24  4055.7 1357.95  4105.1 1355.42  4175.9 1349.52
  4317.8  1341.4  4423.4 1335.65  4479.9 1334.07    4487 1330.82  4522.3 1329.99
  4536.5 1328.49  4543.5 1330.81  4585.9 1329.62  4639.4 1327.23  4776.9 1322.43
  4868.8 1321.76  4946.6 1319.39  4974.9 1317.14    4982 1318.06  5001.1 1315.24
  5001.4 1314.74  5005.1 1315.24  5009.4  1317.8  5019.4 1320.15    5049 1322.84
  5068.9 1324.33  5134.7 1327.65  5209.4 1333.18  5363.6  1341.7  5372.6 1342.15
#Mann= 12 ,-1 , 0
  4048.6     .12       0  4049.7     .05       0  4175.9     .12       0
  4317.8     .05       0  4585.9     .12       0  4639.4     .05       0
  5001.1     .05       0  5005.1     .05       0    5049     .12       0
  5068.9     .05       0  5209.4     .12       0  5363.6     .05       0
Bank Sta=5001.1,5005.1
XS Rating Curve= 0 ,0
Exp/Cntr=0.3,0.1

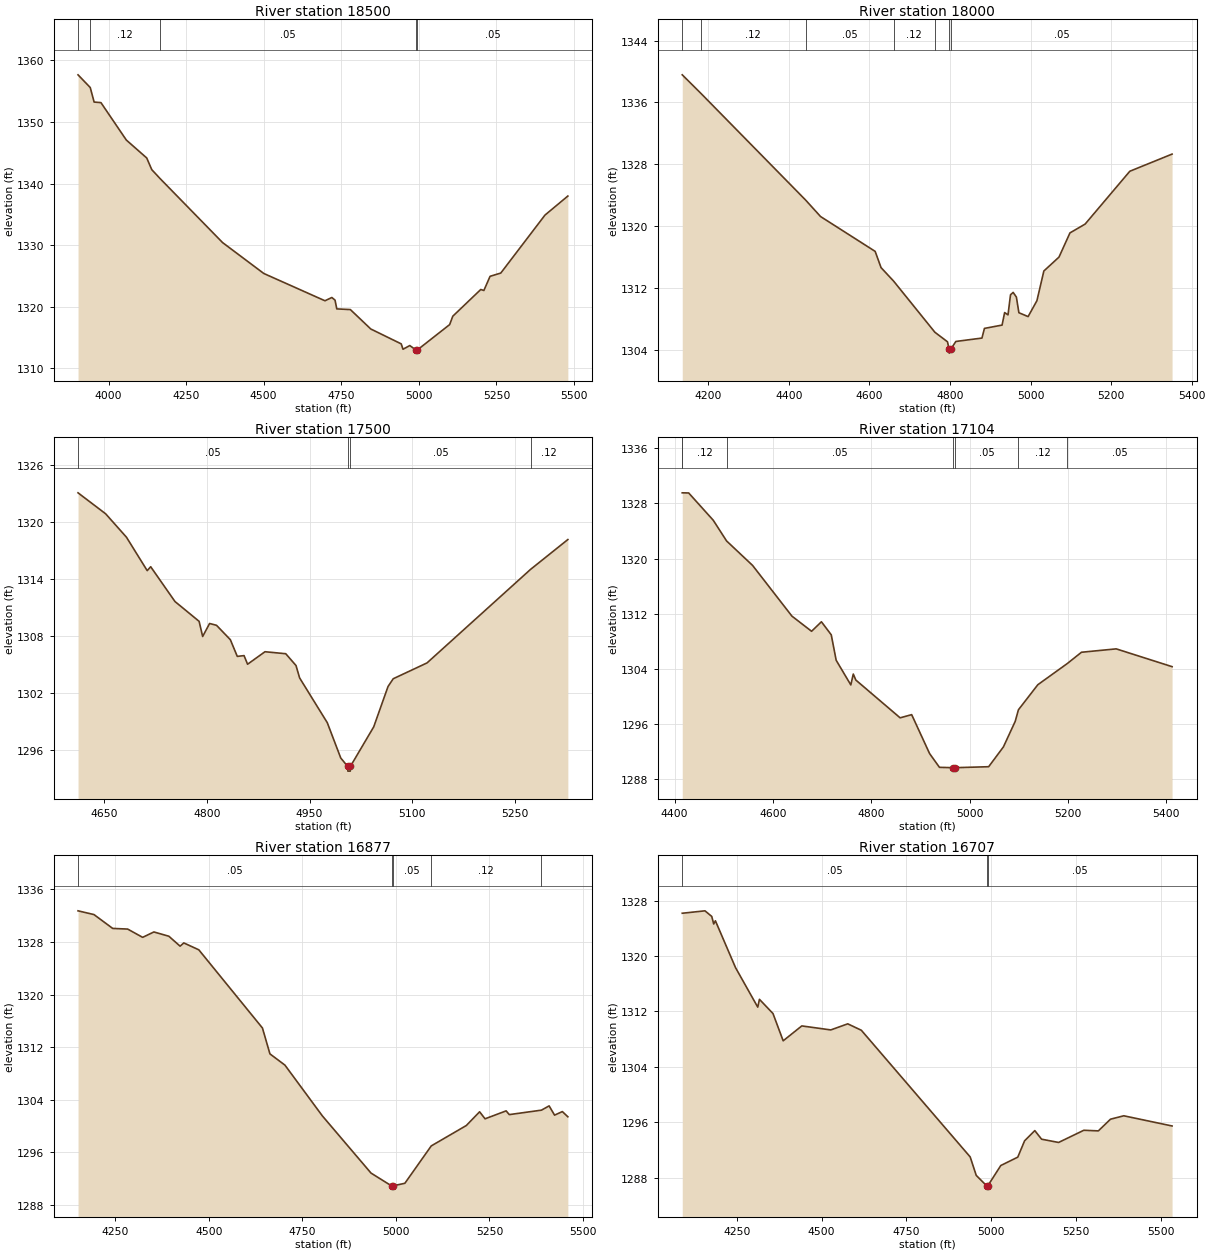
Type RM Length L Ch R = 1 ,18500   ,500,500,500
BEGIN DESCRIPTION:
SANFERNANDO033 37.0
END DESCRIPTION:
XS GIS Cut Line= 3
      2778305.69     10281103.12      2777784.77     10280136.33
      2777305.72     10280103.11
#Sta/Elev= 30
  3901.8 1357.65  3941.1 1355.59  3953.7 1353.23  3975.6 1353.14  4057.5 1347.06
  4123.2 1344.15  4139.5 1342.25  4167.5 1340.74  4367.5 1330.42  4500.4  1325.4
  4697.5 1320.97  4719.7  1321.5    4730 1321.07  4735.6 1319.65  4779.4 1319.54
  4845.1 1316.39  4943.3 1313.97    4949  1313.1  4970.9  1313.7  4990.8 1312.97
    4991 1312.47  4994.8 1312.97  5099.3  1317.1  5109.4 1318.46  5199.6  1322.8
  5209.6 1322.64  5229.6 1324.94  5264.1 1325.47  5406.5 1334.88  5480.2 1337.97
#Mann= 5 ,-1 , 0
  3901.8     .05       0  3941.1     .12       0  4167.5     .05       0
  4990.8     .05       0  4994.8     .05       0
Bank Sta=4990.8,4994.8
XS Rating Curve= 0 ,0
Exp/Cntr=0.3,0.1

Type RM Length L Ch R = 1 ,18000   ,500,500,500
BEGIN DESCRIPTION:
SANFERNANDO033 36.0
END DESCRIPTION:
XS GIS Cut Line= 3
      2778355.67     10278953.14      2777840.88     10279647.78
      2777505.65     10279753.12
#Sta/Elev= 30
  4135.4 1339.56  4182.1 1337.14  4441.5 1323.36  4478.7 1321.22  4614.3 1316.71
  4628.9 1314.61  4660.3 1312.85  4762.6 1306.24  4793.8 1305.01    4798 1304.04
  4798.3 1303.54    4802 1304.04  4814.6 1305.05  4879.4 1305.49  4885.6 1306.74
  4929.4 1307.17  4935.7 1308.79  4944.1 1308.49  4950.3 1311.09  4956.8  1311.4
  4964.9  1310.8  4971.1 1308.77    4994 1308.27  5015.9 1310.33  5033.1 1314.17
  5070.7 1315.97  5097.9  1319.1  5135.5 1320.24  5246.5 1327.08  5351.4  1329.3
#Mann= 7 ,-1 , 0
  4135.4     .05       0  4182.1     .12       0  4441.5     .05       0
  4660.3     .12       0  4762.6     .05       0    4798     .03       0
    4802     .05       0
Bank Sta=4798,4802
XS Rating Curve= 0 ,0
Exp/Cntr=0.3,0.1

Type RM Length L Ch R = 1 ,17500   ,396,396,396
BEGIN DESCRIPTION:
SANFERNANDO033 35.0
END DESCRIPTION:
XS GIS Cut Line= 3
      2778105.65     10279153.12      2777721.85     10279208.02
      2777505.69     10279453.11
#Sta/Elev= 30
  4612.3 1323.09  4652.7 1320.87    4683  1318.4  4713.2 1314.88  4718.3 1315.29
  4753.7 1311.62  4788.9 1309.53  4794.1 1307.93  4804.2  1309.3  4814.3 1309.11
  4834.5 1307.59  4844.6 1305.83  4854.5 1305.91  4859.6    1305    4885 1306.32
  4915.3 1306.11  4930.3 1304.86  4935.5 1303.56  4975.9 1298.83  4995.5 1295.11
  5005.6 1294.22  5005.9 1293.72  5009.4 1293.72  5009.6 1294.22  5043.6 1298.39
  5064.5 1302.65  5072.1 1303.47  5121.4 1305.14  5272.4 1315.01  5326.8 1318.16
#Mann= 4 ,-1 , 0
  4612.3     .05       0  5005.6     .05       0  5009.6     .05       0
  5272.4     .12       0
Bank Sta=5005.6,5009.6
XS Rating Curve= 0 ,0
Exp/Cntr=0.3,0.1

Type RM Length L Ch R = 1 ,17104   ,227,227,227
BEGIN DESCRIPTION:
Mapping XS 7eda21c8
END DESCRIPTION:
XS GIS Cut Line= 4
      2778198.74     10278820.03      2777732.13     10278830.88
      2777417.46     10278841.73      2777265.57     10278993.62
#Sta/Elev= 30
  4415.6 1329.54    4416 1329.54  4428.7 1329.52  4478.7 1325.56  4505.8 1322.56
  4558.7 1319.01  4638.7 1311.66  4678.7 1309.46  4698.7 1310.84  4718.7 1308.95
  4728.7 1305.26  4758.5 1301.68  4763.5 1303.26  4768.7 1302.39  4858.8 1296.91
  4882.3 1297.37  4918.8 1291.72  4938.8 1289.73  4966.8 1289.68  4967.1 1289.18
  4970.8 1289.68  5038.9 1289.82  5068.9 1292.69    5093 1296.41  5099.4 1298.07
  5138.9 1301.71    5199 1304.79  5227.7 1306.42  5298.4 1306.91    5412 1304.33
#Mann= 7 ,-1 , 0
  4415.6     .05       0    4416     .12       0  4505.8     .05       0
  4966.8     .05       0  4970.8     .05       0  5099.4     .12       0
    5199     .05       0
Bank Sta=4966.8,4970.8
XS Rating Curve= 0 ,0
Exp/Cntr=0.3,0.1

Type RM Length L Ch R = 1 ,16877   ,170,170,170
BEGIN DESCRIPTION:
Mapping XS 0f406869
END DESCRIPTION:
XS GIS Cut Line= 4
      2778448.29     10278570.46      2777656.17     10278603.02
      2777450.01     10278624.72      2777201.27     10278808.57
#Sta/Elev= 30
  4150.3 1332.75  4192.9 1332.18    4243 1330.07    4283 1329.97    4323 1328.71
  4353.1 1329.53  4393.1 1328.88  4423.1 1327.37  4433.1 1327.86  4473.2 1326.81
  4643.3  1314.9  4663.3 1310.96  4703.4 1309.25  4803.5 1301.51  4933.6  1292.8
  4988.3 1290.86  4988.5 1290.36  4992.3 1290.86    5024 1291.25  5094.5 1296.94
  5188.3 1300.05  5223.8 1302.14  5238.4 1301.07  5294.7 1302.28  5303.1 1301.71
  5389.2 1302.39  5409.6 1303.04  5424.2 1301.63    5445 1302.17  5459.7 1301.38
#Mann= 5 ,-1 , 0
  4150.3     .05       0  4988.3     .05       0  4992.3     .05       0
  5094.5     .12       0  5389.2     .05       0
Bank Sta=4988.3,4992.3
XS Rating Curve= 0 ,0
Exp/Cntr=0.3,0.1

Type RM Length L Ch R = 1 ,16707   ,589,589,589
BEGIN DESCRIPTION:
Mapping XS 7b83c1f8
END DESCRIPTION:
XS GIS Cut Line= 3
      2778492.45     10278370.88      2777372.61     10278457.69
      2777073.12     10278574.88
#Sta/Elev= 30
  4088.9 1326.18  4155.9 1326.53  4175.9 1325.72  4181.7 1324.63  4186.7 1325.09
  4246.1 1318.32  4311.6 1312.62  4316.6 1313.75  4356.5  1311.7  4386.6 1307.76
  4441.5 1309.91    4527 1309.33  4577.1 1310.21  4617.2 1309.28  4938.2 1290.99
    4956 1288.33  4986.4 1286.84  4986.6 1286.34  4990.4 1286.84  5028.5 1289.75
  5078.6 1290.96  5098.7 1293.32  5128.8 1294.79  5148.8 1293.55    5199 1293.08
  5273.4 1294.84  5316.2 1294.75  5352.1 1296.44  5391.3 1296.93  5533.7 1295.46
#Mann= 3 ,-1 , 0
  4088.9     .05       0  4986.4     .03       0  4990.4     .05       0
Bank Sta=4986.4,4990.4
XS Rating Curve= 0 ,0
Exp/Cntr=0.3,0.1

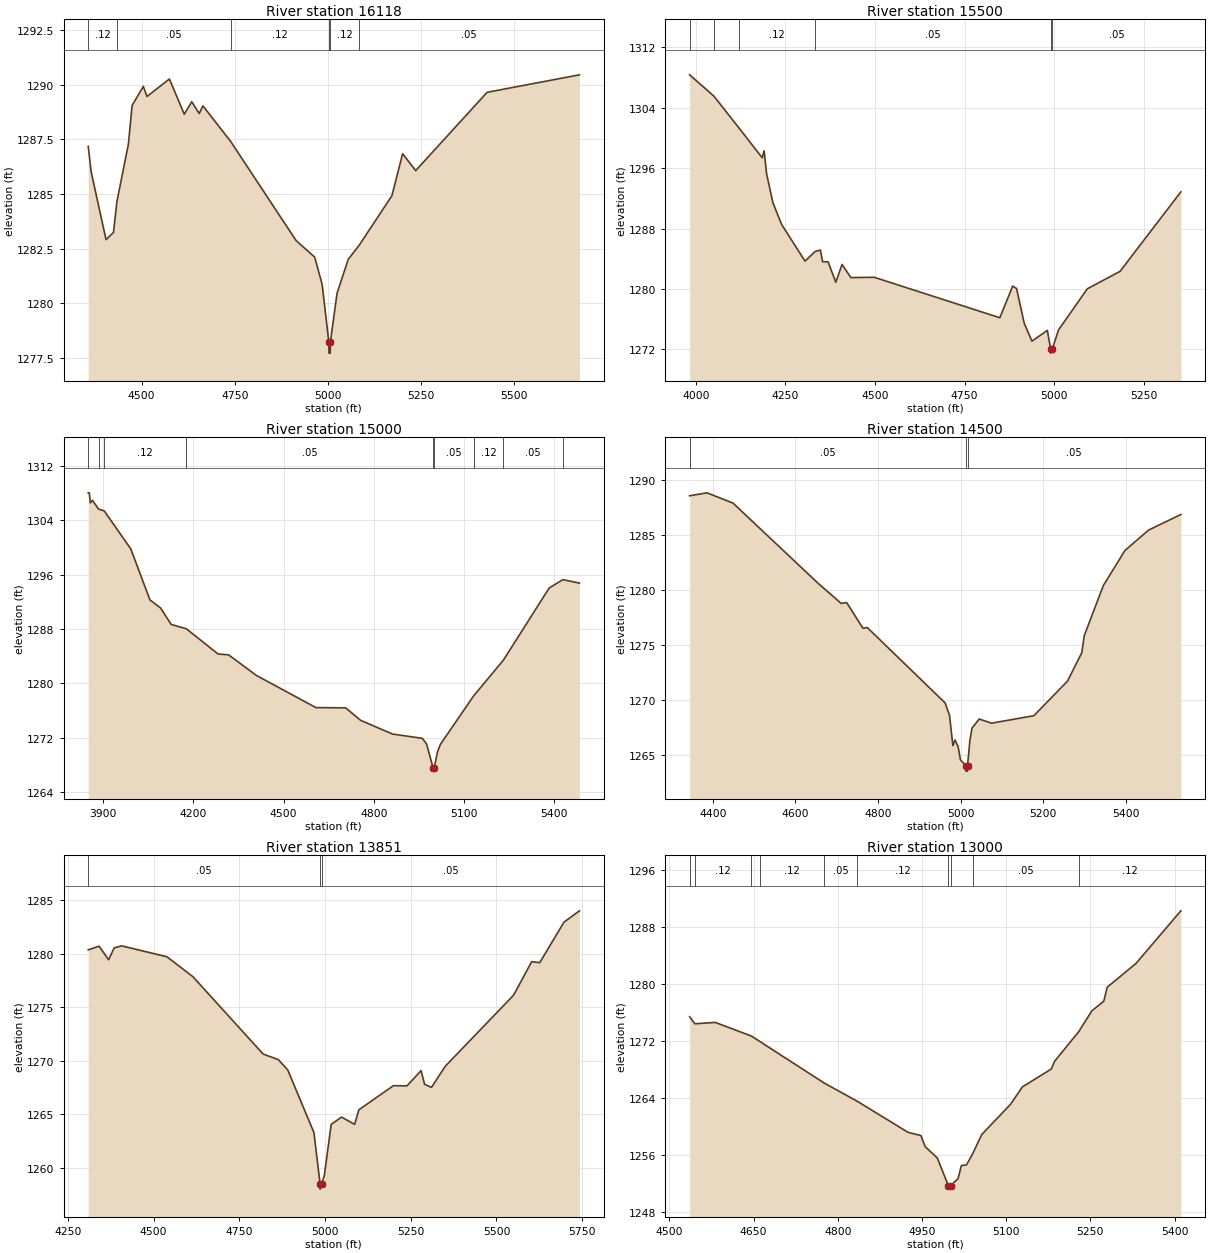
Type RM Length L Ch R = 1 ,16118   ,618,618,618
BEGIN DESCRIPTION:
Mapping XS f4ad0b0b
END DESCRIPTION:
XS GIS Cut Line= 3
      2778123.51     10277910.81      2777394.31     10277910.81
      2777021.03     10278366.56
#Sta/Elev= 30
  4356.9 1287.18  4364.7 1286.02  4404.7 1282.91  4424.7 1283.24  4433.9 1284.65
  4464.7 1287.28  4474.7 1289.05  4504.7 1289.92  4514.7 1289.46  4574.7 1290.26
  4614.7 1288.65  4634.7 1289.22  4654.7 1288.68  4664.7 1289.03  4738.9 1287.41
  4914.7 1282.87  4964.7 1282.11  4984.7 1280.86  5002.7 1278.22    5003 1277.72
  5006.5 1277.72  5006.7 1278.22  5024.7 1280.46  5054.7 1282.01  5083.9 1282.65
  5171.9 1284.92  5200.6 1286.84  5235.8 1286.07  5427.4 1289.65  5675.2 1290.45
#Mann= 6 ,-1 , 0
  4356.9     .12       0  4433.9     .05       0  4738.9     .12       0
  5002.7     .07       0  5006.7     .12       0  5083.9     .05       0
Bank Sta=5002.7,5006.7
XS Rating Curve= 0 ,0
Exp/Cntr=0.3,0.1

Type RM Length L Ch R = 1 ,15500   ,500,500,500
BEGIN DESCRIPTION:
SANFERNANDO033 31.0
END DESCRIPTION:
XS GIS Cut Line= 3
       2778305.7     10277703.12      2777357.79     10277333.58
       2777005.7     10277303.11
#Sta/Elev= 30
  3982.6 1308.33    4050 1305.53  4120.7 1301.28  4185.1 1297.36  4190.5 1298.27
  4197.3 1295.27    4215 1291.41  4239.5 1288.52  4304.6 1283.69  4332.9 1284.97
  4347.5 1285.15  4353.6 1283.62    4369 1283.59  4390.5  1280.9    4408 1283.25
  4432.5 1281.51  4497.8 1281.55  4848.2  1276.2  4884.2 1280.39  4894.9 1280.06
  4916.4 1275.46  4937.9  1273.1  4980.8 1274.53  4990.2 1272.02  4990.4 1271.52
  4994.3 1272.02  5012.1 1274.59  5092.4 1280.03  5183.6 1282.33  5353.4 1292.85
#Mann= 6 ,-1 , 0
  3982.6     .12       0    4050     .05       0  4120.7     .12       0
  4332.9     .05       0  4990.2     .03       0  4994.3     .05       0
Bank Sta=4990.2,4994.3
XS Rating Curve= 0 ,0
Exp/Cntr=0.3,0.1

Type RM Length L Ch R = 1 ,15000   ,500,500,500
BEGIN DESCRIPTION:
SANFERNANDO033 30.0
END DESCRIPTION:
XS GIS Cut Line= 3
      2778255.71     10277653.14      2777437.22     10276846.74
      2776955.69     10276803.11
#Sta/Elev= 30
    3851 1308.02  3854.5 1308.02  3858.1 1306.53  3865.1 1306.92  3885.4 1305.63
  3904.2 1305.36  3992.4 1299.78  4056.1 1292.28  4091.4 1291.09  4126.8 1288.67
  4176.9 1288.04  4282.4 1284.33  4317.7  1284.2  4409.7 1281.18  4607.7 1276.45
  4706.7 1276.41  4756.2 1274.58  4862.2 1272.56  4961.2 1271.93  4975.3 1271.12
  4996.9 1267.61  4997.2 1267.11  5001.1 1267.61  5011.6 1269.93  5021.6 1271.06
  5131.9 1278.17  5230.7 1283.42  5383.1 1294.04  5428.3 1295.26  5483.5 1294.75
#Mann= 9 ,-1 , 0
    3851     .12       0  3885.4     .05       0  3904.2     .12       0
  4176.9     .05       0  4996.9     .05       0  5001.1     .05       0
  5131.9     .12       0  5230.7     .05       0  5428.3     .12       0
Bank Sta=4996.9,5001.1
XS Rating Curve= 0 ,0
Exp/Cntr=0.3,0.1

Type RM Length L Ch R = 1 ,14500   ,649,649,649
BEGIN DESCRIPTION:
SANFERNANDO033 29.0
END DESCRIPTION:
XS GIS Cut Line= 3
      2778255.67     10276603.11      2777630.29     10276403.37
      2777105.69     10276503.11
#Sta/Elev= 30
  4343.5  1288.6  4385.5 1288.87  4448.5 1287.94  4654.4 1280.66  4710.9 1278.81
  4724.1 1278.89  4763.4 1276.56  4773.9 1276.62  4962.8 1269.76  4973.3 1268.64
  4981.5 1265.88  4986.8 1266.39  4994.3 1265.77  4999.8 1264.59  5012.7 1264.06
    5013 1263.56  5016.7 1263.56    5017 1264.06  5022.7 1266.34  5027.8 1267.47
  5045.4  1268.3  5074.9 1267.92  5177.7  1268.6  5259.2 1271.74  5293.9 1274.33
  5299.9 1275.88  5346.2 1280.44  5398.4 1283.62  5455.7 1285.48    5534  1286.9
#Mann= 3 ,-1 , 0
  4343.5     .05       0  5012.7     .05       0    5017     .05       0
Bank Sta=5012.7,5017
XS Rating Curve= 0 ,0
Exp/Cntr=0.3,0.1

Type RM Length L Ch R = 1 ,13851   ,851,851,851
BEGIN DESCRIPTION:
Mapping XS dca68f88
END DESCRIPTION:
XS GIS Cut Line= 4
      2778245.68     10276184.65      2777731.36     10275912.36
      2777116.18     10275993.04      2776904.41      10276083.8
#Sta/Elev= 30
  4309.3 1280.37  4341.1 1280.71  4368.8 1279.44  4385.1 1280.56  4407.1 1280.74
  4539.1 1279.72  4614.8 1277.85  4819.5 1270.62  4863.7  1270.1  4891.3 1269.13
  4967.6 1263.28  4985.6 1258.48  4985.9 1257.98  4989.9 1258.48  4997.8 1259.22
    5018 1264.04  5048.3 1264.72  5086.4 1264.04  5098.7  1265.4  5199.5 1267.66
    5239 1267.64  5280.2 1269.07  5290.3  1267.8  5310.5  1267.5  5350.8 1269.48
  5550.1 1276.13  5602.7 1279.26  5626.3 1279.17    5697 1282.96  5742.1 1284.02
#Mann= 3 ,-1 , 0
  4309.3     .05       0  4985.6     .05       0  4989.9     .05       0
Bank Sta=4985.6,4989.9
XS Rating Curve= 0 ,0
Exp/Cntr=0.3,0.1

Type RM Length L Ch R = 1 ,13000   ,500,500,500
BEGIN DESCRIPTION:
SANFERNANDO033 26.0
END DESCRIPTION:
XS GIS Cut Line= 3
      2777805.67     10275753.09      2777579.96      10275347.8
       2777355.7     10275003.14
#Sta/Elev= 30
  4536.1 1275.42  4545.5 1274.43  4581.8 1274.62  4646.1 1272.71  4660.7 1271.97
  4775.9  1266.1  4834.4 1263.56  4925.2 1259.18  4948.1 1258.73  4955.6 1257.18
  4977.4 1255.57  4996.9  1251.7  4997.2  1251.2    5001  1251.2  5001.3  1251.7
  5014.3 1252.67  5020.2 1254.51  5029.4 1254.61  5040.3 1256.16  5056.5 1258.87
  5107.8 1263.12  5128.9 1265.56  5180.3 1268.07  5186.3 1269.17    5229 1273.29
  5252.8 1276.26  5273.9  1277.6    5280 1279.57  5331.2  1282.9  5411.2  1290.3
#Mann= 10 ,-1 , 0
  4536.1     .05       0  4545.5     .12       0  4646.1     .05       0
  4660.7     .12       0  4775.9     .05       0  4834.4     .12       0
  4996.9     .07       0  5001.3     .12       0  5040.3     .05       0
    5229     .12       0
Bank Sta=4996.9,5001.3
XS Rating Curve= 0 ,0
Exp/Cntr=0.3,0.1

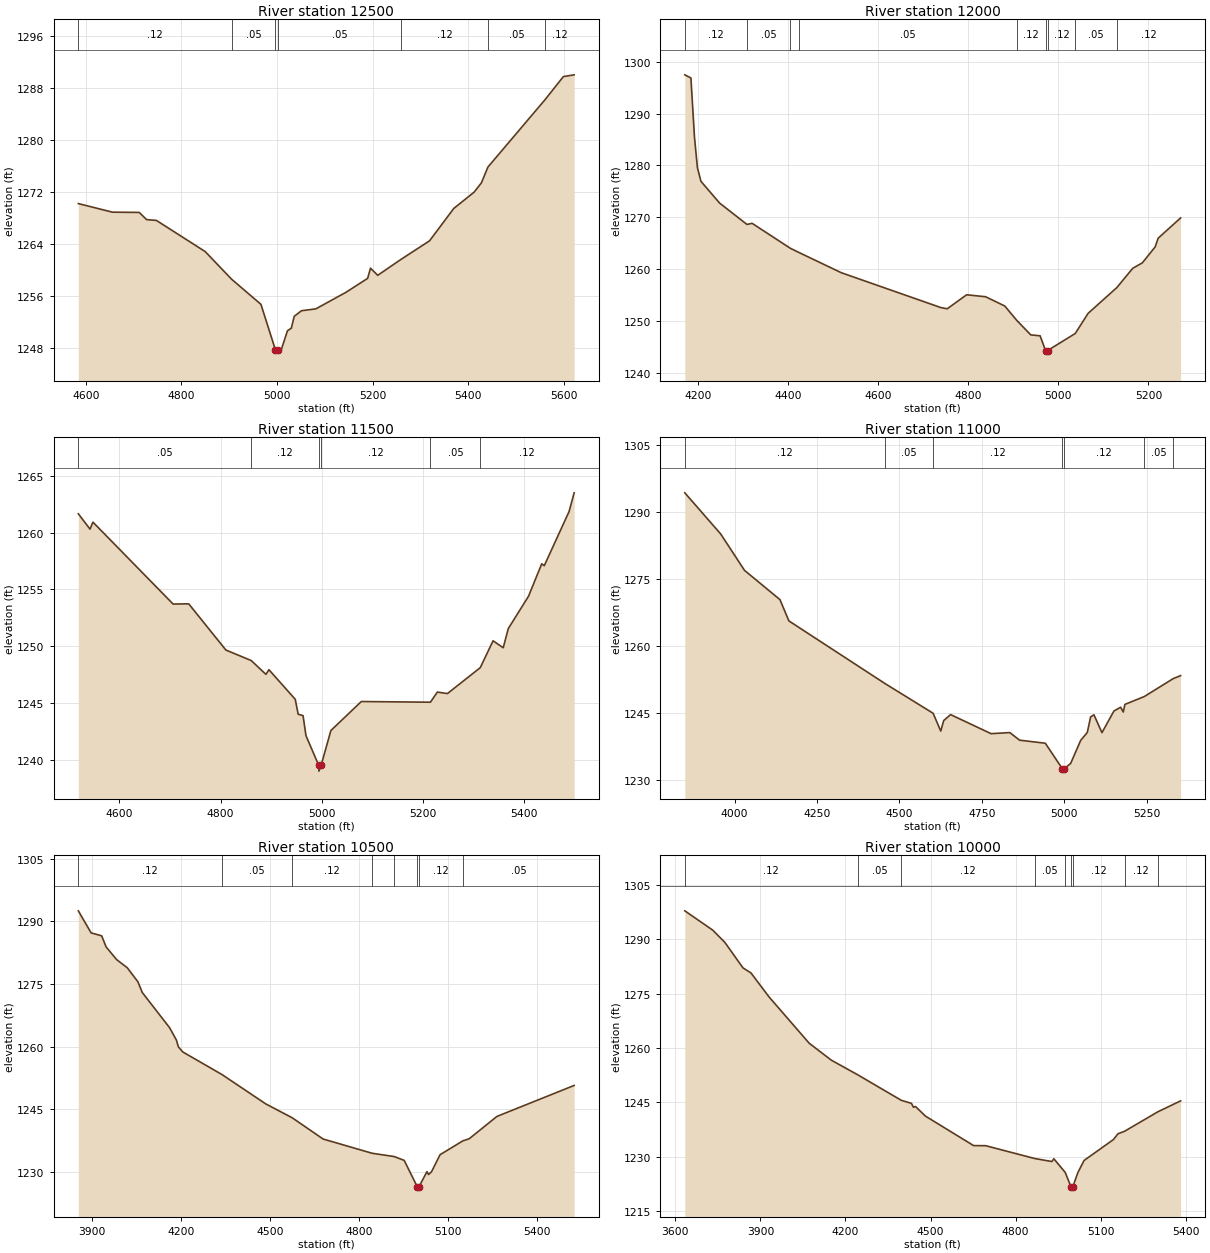
Type RM Length L Ch R = 1 ,12500   ,500,500,500
BEGIN DESCRIPTION:
SANFERNANDO033 25.0
END DESCRIPTION:
XS GIS Cut Line= 3
      2778105.69     10275553.13      2778023.94     10275145.86
      2777505.72     10274803.13
#Sta/Elev= 30
  4584.6 1270.18  4655.9 1268.86  4711.9 1268.82  4727.4 1267.71  4747.8 1267.59
  4849.8 1262.79  4905.2 1258.52  4966.4 1254.66  4996.7 1247.64    4997 1247.14
  5001.1 1247.64    5009 1247.69  5021.9 1250.59    5030 1250.99    5036 1252.81
  5051.1 1253.67  5081.2 1253.96  5144.4 1256.52  5189.5 1258.66  5195.5 1260.23
  5210.6 1259.13    5260 1261.62  5318.9 1264.44  5369.6 1269.43  5412.2 1271.95
  5427.3 1273.37    5441 1275.81  5560.2 1286.17  5598.8 1289.75  5621.3 1290.02
#Mann= 7 ,-1 , 0
  4584.6     .12       0  4905.2     .05       0  4996.7     .05       0
  5001.1     .05       0    5260     .12       0    5441     .05       0
  5560.2     .12       0
Bank Sta=4996.7,5001.1
XS Rating Curve= 0 ,0
Exp/Cntr=0.3,0.1

Type RM Length L Ch R = 1 ,12000   ,500,500,500
BEGIN DESCRIPTION:
SANFERNANDO033 24.0
END DESCRIPTION:
XS GIS Cut Line= 3
      2779055.65     10275353.09      2778410.05     10274831.93
      2778205.65     10274653.08
#Sta/Elev= 30
  4170.3 1297.48  4183.9 1296.88  4191.8 1285.47  4198.3 1279.59  4206.2 1276.94
  4247.8 1272.74  4308.4 1268.63  4319.8 1268.85  4404.7 1264.04  4423.2 1263.25
  4518.1 1259.32  4738.8 1252.61  4753.2 1252.37  4796.3 1255.07  4838.5 1254.69
  4881.1  1252.9  4907.4 1250.16  4938.7 1247.34  4959.5 1247.16  4971.6 1244.32
  4971.9 1243.82  4976.2 1244.32  5037.6 1247.61  5066.1 1251.49  5129.7 1256.44
  5165.3 1260.18  5186.6 1261.23  5215.1 1264.31  5221.7 1265.98  5271.6 1269.89
#Mann= 9 ,-1 , 0
  4170.3     .12       0  4308.4     .05       0  4404.7     .12       0
  4423.2     .05       0  4907.4     .12       0  4971.6     .07       0
  4976.2     .12       0  5037.6     .05       0  5129.7     .12       0
Bank Sta=4971.6,4976.2
XS Rating Curve= 0 ,0
Exp/Cntr=0.3,0.1

Type RM Length L Ch R = 1 ,11500   ,500,500,500
BEGIN DESCRIPTION:
SANFERNANDO033 23.0
END DESCRIPTION:
XS GIS Cut Line= 3
      2779055.67     10275003.09      2778804.14     10274592.63
       2778305.7     10274553.11
#Sta/Elev= 30
  4518.6 1261.65  4541.7  1260.3  4547.6 1260.91  4706.2 1253.71  4737.1 1253.73
  4810.6 1249.67  4860.9 1248.74  4889.9 1247.53  4895.8 1247.94  4947.9 1245.34
  4953.8 1244.02  4963.4  1243.9  4969.2 1242.14  4994.5 1239.52  4994.8 1239.02
  4999.1 1239.52  5018.5 1242.59  5078.7 1245.14  5215.5 1245.08  5229.2 1245.97
  5249.2 1245.84  5314.2 1248.12  5339.5 1250.48  5359.6 1249.87  5369.6 1251.55
  5409.7  1254.4  5435.8 1257.25  5440.8 1257.08    5490 1261.85    5500 1263.49
#Mann= 6 ,-1 , 0
  4518.6     .05       0  4860.9     .12       0  4994.5     .07       0
  4999.1     .12       0  5215.5     .05       0  5314.2     .12       0
Bank Sta=4994.5,4999.1
XS Rating Curve= 0 ,0
Exp/Cntr=0.3,0.1

Type RM Length L Ch R = 1 ,11000   ,500,500,500
BEGIN DESCRIPTION:
SANFERNANDO033 22.0
END DESCRIPTION:
XS GIS Cut Line= 3
       2779755.7     10274753.12      2778804.86     10274104.68
      2778455.64     10274053.11
#Sta/Elev= 30
  3849.1 1294.28  3958.1 1285.07  4030.1 1276.95  4137.8 1270.39  4164.8 1265.64
    4455 1251.69  4602.3 1244.98  4625.5    1241  4634.4 1243.35  4655.4 1244.68
    4778 1240.42  4834.9 1240.66  4864.7 1238.96  4942.6 1238.28  4994.6 1232.54
  4994.9 1232.04  4999.4 1232.54  5019.4 1233.76  5049.9 1238.92  5069.9 1240.68
    5080 1244.16  5090.1 1244.64  5114.4 1240.64  5150.8 1245.49    5171 1246.33
    5179 1245.26    5184 1246.96  5242.8 1248.72  5330.3 1252.72    5353  1253.4
#Mann= 7 ,-1 , 0
  3849.1     .12       0    4455     .05       0  4602.3     .12       0
  4994.6     .07       0  4999.4     .12       0  5242.8     .05       0
  5330.3     .12       0
Bank Sta=4994.6,4999.4
XS Rating Curve= 0 ,0
Exp/Cntr=0.3,0.1

Type RM Length L Ch R = 1 ,10500   ,500,500,500
BEGIN DESCRIPTION:
SANFERNANDO033 21.0
END DESCRIPTION:
XS GIS Cut Line= 3
      2780005.67      10274353.1      2779068.27     10273692.11
      2778555.66     10273803.12
#Sta/Elev= 30
    3853 1292.52  3896.1 1287.24  3931.8 1286.53  3946.6 1283.88  3982.3 1280.83
    4018 1278.89  4053.7 1275.54  4068.5 1272.97  4160.8 1264.52  4183.4  1261.6
  4190.4 1259.93  4205.2 1258.72  4337.1 1253.32  4484.7 1246.29    4574 1242.96
  4678.1 1237.87  4843.3 1234.46  4917.9 1233.67  4951.5 1232.76  4996.1 1226.37
  4996.5 1225.87  5000.9 1226.37  5028.3 1230.06  5033.4 1229.36  5043.6 1230.02
  5072.4 1234.11    5149 1237.42  5170.8 1237.94  5264.1 1243.28  5524.5  1250.7
#Mann= 8 ,-1 , 0
    3853     .12       0  4337.1     .05       0    4574     .12       0
  4843.3     .05       0  4917.9     .12       0  4996.1     .07       0
  5000.9     .12       0    5149     .05       0
Bank Sta=4996.1,5000.9
XS Rating Curve= 0 ,0
Exp/Cntr=0.3,0.1

Type RM Length L Ch R = 1 ,10000   ,500,500,500
BEGIN DESCRIPTION:
SANFERNANDO033 20.0
END DESCRIPTION:
XS GIS Cut Line= 3
       2780205.7     10274203.13      2779240.73     10273235.72
      2778905.67      10273053.1
#Sta/Elev= 30
  3633.6 1297.83  3732.6 1292.48    3775 1289.11  3838.7  1282.1    3867 1280.69
  3930.6 1274.09    4072 1261.33  4149.8 1256.66  4243.5  1252.6  4396.9 1245.57
  4432.7 1244.73  4439.7 1243.66  4446.8 1243.87  4482.1 1241.21  4651.9 1233.08
  4694.3 1233.06  4866.7 1229.53  4927.6 1228.69  4934.7 1229.45  4974.8 1225.68
  4995.8 1221.58  4996.2 1221.08  5000.8 1221.58  5019.4 1225.65  5041.2 1228.98
  5144.7 1234.75  5160.8 1236.35  5184.1 1237.04  5301.4 1242.41  5381.6 1245.42
#Mann= 9 ,-1 , 0
  3633.6     .12       0  4243.5     .05       0  4396.9     .12       0
  4866.7     .05       0  4974.8     .12       0  4995.8     .07       0
  5000.8     .12       0  5184.1     .12       0  5301.4     .05       0
Bank Sta=4995.8,5000.8
XS Rating Curve= 0 ,0
Exp/Cntr=0.3,0.1

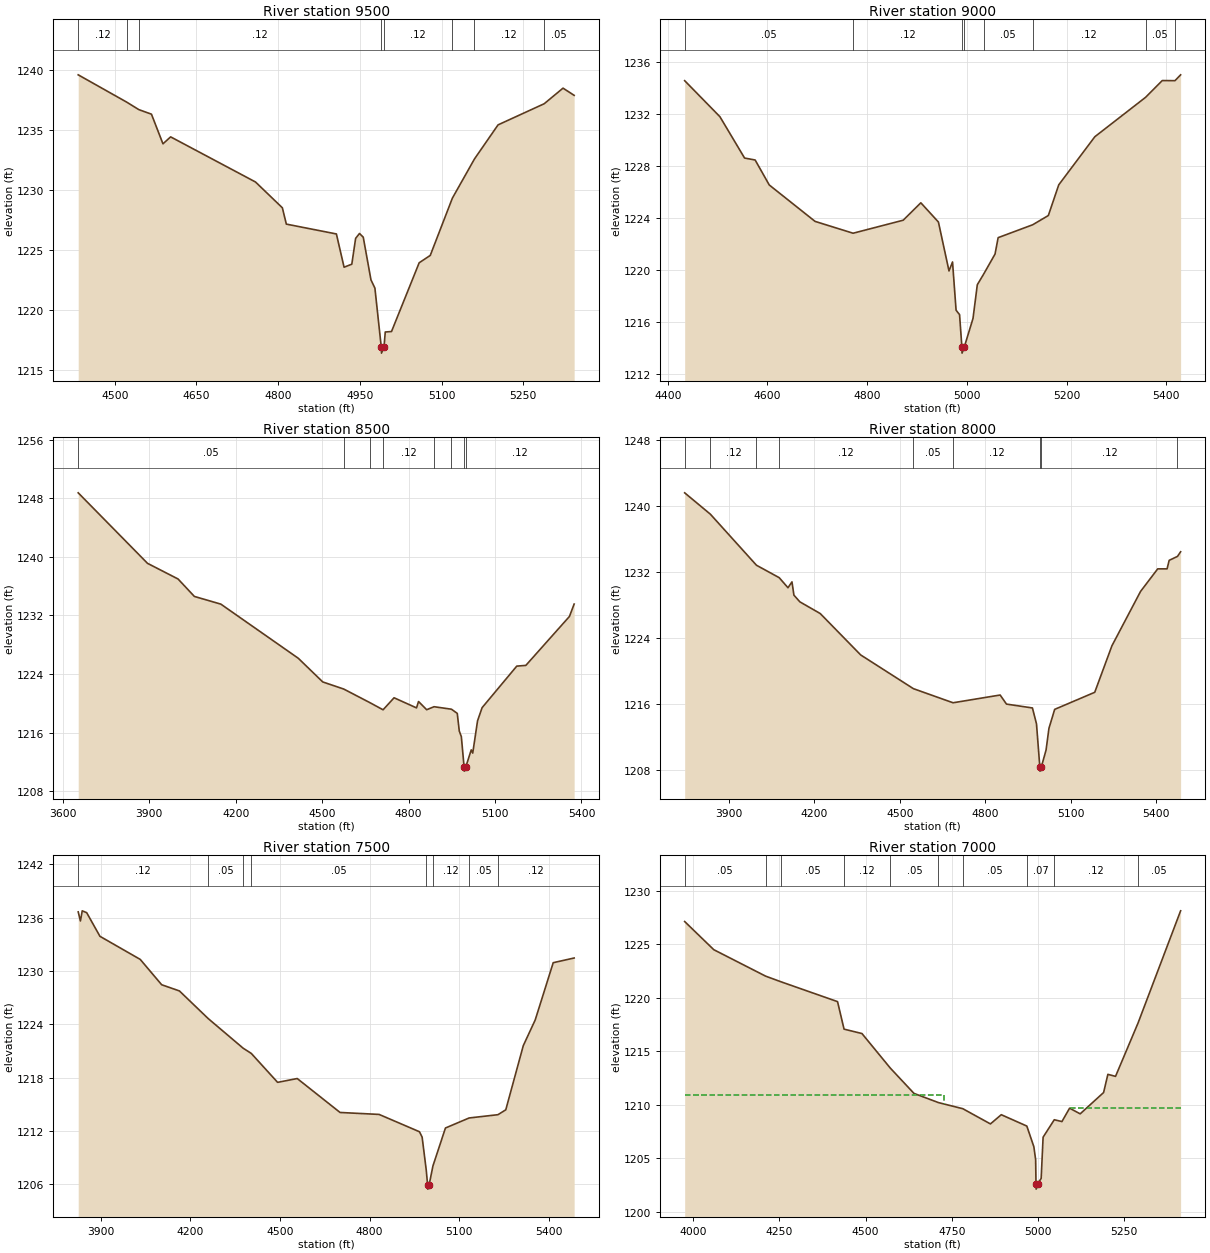
Type RM Length L Ch R = 1 ,9500    ,500,500,500
BEGIN DESCRIPTION:
SANFERNANDO033 19.0
END DESCRIPTION:
XS GIS Cut Line= 3
      2779855.71     10273253.14      2779443.78     10272863.52
      2779105.64      10272803.1
#Sta/Elev= 30
    4433 1239.57  4522.2 1237.29  4544.3 1236.67  4567.5 1236.29  4588.6 1233.82
  4602.7  1234.4  4758.5 1230.64  4807.8 1228.49  4815.1 1227.13    4907 1226.31
  4921.1 1223.54  4935.3 1223.79  4942.3 1225.94  4949.4 1226.35  4956.3 1226.04
  4970.5 1222.48  4977.7  1221.8  4989.4 1216.88  4989.8 1216.38  4994.4 1216.88
  4996.7 1218.14  5008.2 1218.18    5059 1223.91  5079.3 1224.52  5119.9 1229.29
  5160.5 1232.56  5203.8  1235.4  5288.5 1237.16  5323.1 1238.46  5343.5 1237.86
#Mann= 8 ,-1 , 0
    4433     .12       0  4522.2     .05       0  4544.3     .12       0
  4989.4     .07       0  4994.4     .12       0  5119.9     .05       0
  5160.5     .12       0  5288.5     .05       0
Bank Sta=4989.4,4994.4
XS Rating Curve= 0 ,0
Exp/Cntr=0.3,0.1

Type RM Length L Ch R = 1 ,9000    ,500,500,500
BEGIN DESCRIPTION:
SANFERNANDO033 18.0
END DESCRIPTION:
XS GIS Cut Line= 3
      2779905.69     10272853.12      2779504.59     10272453.63
       2779155.7      10272703.1
#Sta/Elev= 30
  4433.9 1234.53  4504.6 1231.76  4554.1 1228.58  4575.3 1228.43  4603.6 1226.51
  4695.5 1223.71  4771.8  1222.8  4872.3  1223.8  4907.7 1225.14    4943 1223.66
  4964.2  1219.9  4971.3 1220.59  4978.4 1216.88  4985.4 1216.54    4990 1214.08
  4990.4 1213.58  4995.1 1214.08  5012.4 1216.25    5021 1218.84  5033.5 1219.64
  5056.6  1221.2  5062.8 1222.46  5132.1 1223.45  5163.5 1224.16  5184.4 1226.52
  5256.8 1230.22  5358.6 1233.25  5392.1 1234.54  5417.6 1234.53  5428.9 1234.98
#Mann= 8 ,-1 , 0
  4433.9     .05       0  4771.8     .12       0    4990     .07       0
  4995.1     .12       0  5033.5     .05       0  5132.1     .12       0
  5358.6     .05       0  5417.6     .12       0
Bank Sta=4990,4995.1
XS Rating Curve= 0 ,0
Exp/Cntr=0.3,0.1

Type RM Length L Ch R = 1 ,8500    ,500,500,500
BEGIN DESCRIPTION:
SANFERNANDO033 17.0
END DESCRIPTION:
XS GIS Cut Line= 3
      2780455.68      10272953.1      2779513.27     10271991.65
      2779155.64     10272103.12
#Sta/Elev= 30
  3653.7 1248.74  3894.1 1239.12  4000.2 1236.98  4056.8  1234.6  4148.7 1233.55
  4417.4 1226.16  4502.3 1222.93  4575.2 1221.96  4665.1 1220.12  4711.6 1219.13
  4749.7 1220.77  4827.6 1219.39  4834.6 1220.26  4862.9 1219.14  4888.4 1219.55
  4948.8 1219.21    4969 1218.64    4976 1216.23  4983.2 1215.46  4992.9 1211.26
  4993.3 1210.76    4998 1211.26  5017.5 1213.66  5022.7 1213.22  5039.4 1217.63
  5055.2 1219.42  5175.5 1225.09    5207 1225.19  5358.3 1231.87  5374.6 1233.56
#Mann= 8 ,-1 , 0
  3653.7     .05       0  4575.2     .12       0  4665.1     .05       0
  4711.6     .12       0  4888.4     .05       0  4948.8     .12       0
  4992.9     .07       0    4998     .12       0
Bank Sta=4992.9,4998
XS Rating Curve= 0 ,0
Exp/Cntr=0.3,0.1

Type RM Length L Ch R = 1 ,8000    ,500,500,500
BEGIN DESCRIPTION:
SANFERNANDO033 16.0
END DESCRIPTION:
XS GIS Cut Line= 3
       2780655.7     10272353.13      2779688.95     10271551.93
      2779205.71     10271503.11
#Sta/Elev= 30
  3744.4 1241.64  3834.6 1239.05  3996.4 1232.86  4076.3 1231.35  4107.1 1230.13
  4121.1 1230.84    4128 1229.23  4148.8 1228.42  4220.4    1227  4362.4 1221.98
  4547.5 1217.89  4686.7 1216.18  4852.1 1217.12  4874.2 1216.02  4965.4 1215.55
  4979.7 1213.62  4991.4 1208.39  4991.8 1207.89  4996.6 1208.39  5013.3 1210.45
  5023.4 1213.08  5043.5 1215.38  5184.2 1217.45  5244.5 1223.09    5345 1229.68
  5405.3 1232.42  5438.2 1232.42  5445.5 1233.45  5474.7 1233.93  5485.7 1234.49
#Mann= 9 ,-1 , 0
  3744.4     .05       0  3834.6     .12       0  3996.4     .05       0
  4076.3     .12       0  4547.5     .05       0  4686.7     .12       0
  4991.4     .07       0  4996.6     .12       0  5474.7     .05       0
Bank Sta=4991.4,4996.6
XS Rating Curve= 0 ,0
Exp/Cntr=0.3,0.1

Type RM Length L Ch R = 1 ,7500    ,500,500,500
BEGIN DESCRIPTION:
SANFERNANDO033 15.0
END DESCRIPTION:
XS GIS Cut Line= 3
      2780605.69     10272203.11      2779939.28      10271234.4
      2779455.69     10271203.11
#Sta/Elev= 30
  3824.2 1236.66  3831.6 1235.64  3837.7 1236.78  3852.6 1236.57    3897 1233.91
  4031.9 1231.31  4103.6 1228.46  4163.1 1227.76  4259.1 1224.66  4376.6 1221.31
  4403.6 1220.73  4491.8 1217.47  4557.5  1217.9  4700.9 1214.08  4831.6 1213.86
  4966.7 1211.91  4975.6 1211.31  4989.4  1207.6  4993.9 1205.95  4994.3 1205.45
  4999.2 1205.95  5011.8 1208.06  5053.7 1212.33  5132.9 1213.46  5229.5 1213.83
  5255.7 1214.38  5314.3  1221.6  5354.3  1224.5  5414.5 1230.94  5484.6 1231.47
#Mann= 8 ,-1 , 0
  3824.2     .12       0  4259.1     .05       0  4376.6     .12       0
  4403.6     .05       0  4989.4     .05       0  5011.8     .12       0
  5132.9     .05       0  5229.5     .12       0
Bank Sta=4993.9,4999.2
XS Rating Curve= 0 ,0
Exp/Cntr=0.3,0.1

Type RM Length L Ch R = 1 ,7000    ,500,500,500
BEGIN DESCRIPTION:
SANFERNANDO033 14.0
END DESCRIPTION:
XS GIS Cut Line= 3
      2780555.68     10271803.09      2780228.32     10270832.51
      2779855.66      10270653.1
#Sta/Elev= 30
  3975.7 1227.12  4060.1 1224.49  4210.4 1222.02  4256.1 1221.48  4418.9 1219.64
  4437.8 1217.07  4489.7 1216.66  4571.7 1213.44  4640.5 1211.07  4711.6 1210.21
  4782.1 1209.64  4862.2 1208.22  4893.6 1209.08  4967.7 1208.02  4988.1 1206.09
  4993.3 1204.87  4994.3 1202.63  4994.8 1202.13  4999.7 1202.63  5009.3 1203.14
  5014.9 1206.98  5047.3 1208.61  5069.5 1208.44  5091.7 1209.69  5122.4 1209.16
  5190.3 1211.15  5202.7 1212.85  5224.9 1212.66  5289.9 1217.62  5413.6 1228.12
#Mann= 10 ,-1 , 0
  3975.7     .05       0  4210.4     .12       0  4256.1     .05       0
  4437.8     .12       0  4571.7     .05       0  4711.6     .12       0
  4782.1     .05       0  4967.7     .07       0  5047.3     .12       0
  5289.9     .05       0
#XS Ineff= 2 , 0
         4726.59 1210.89  5091.7         1209.71
Permanent Ineff=
       F       F
Bank Sta=4994.3,4999.7
XS Rating Curve= 0 ,0
Exp/Cntr=0.3,0.1