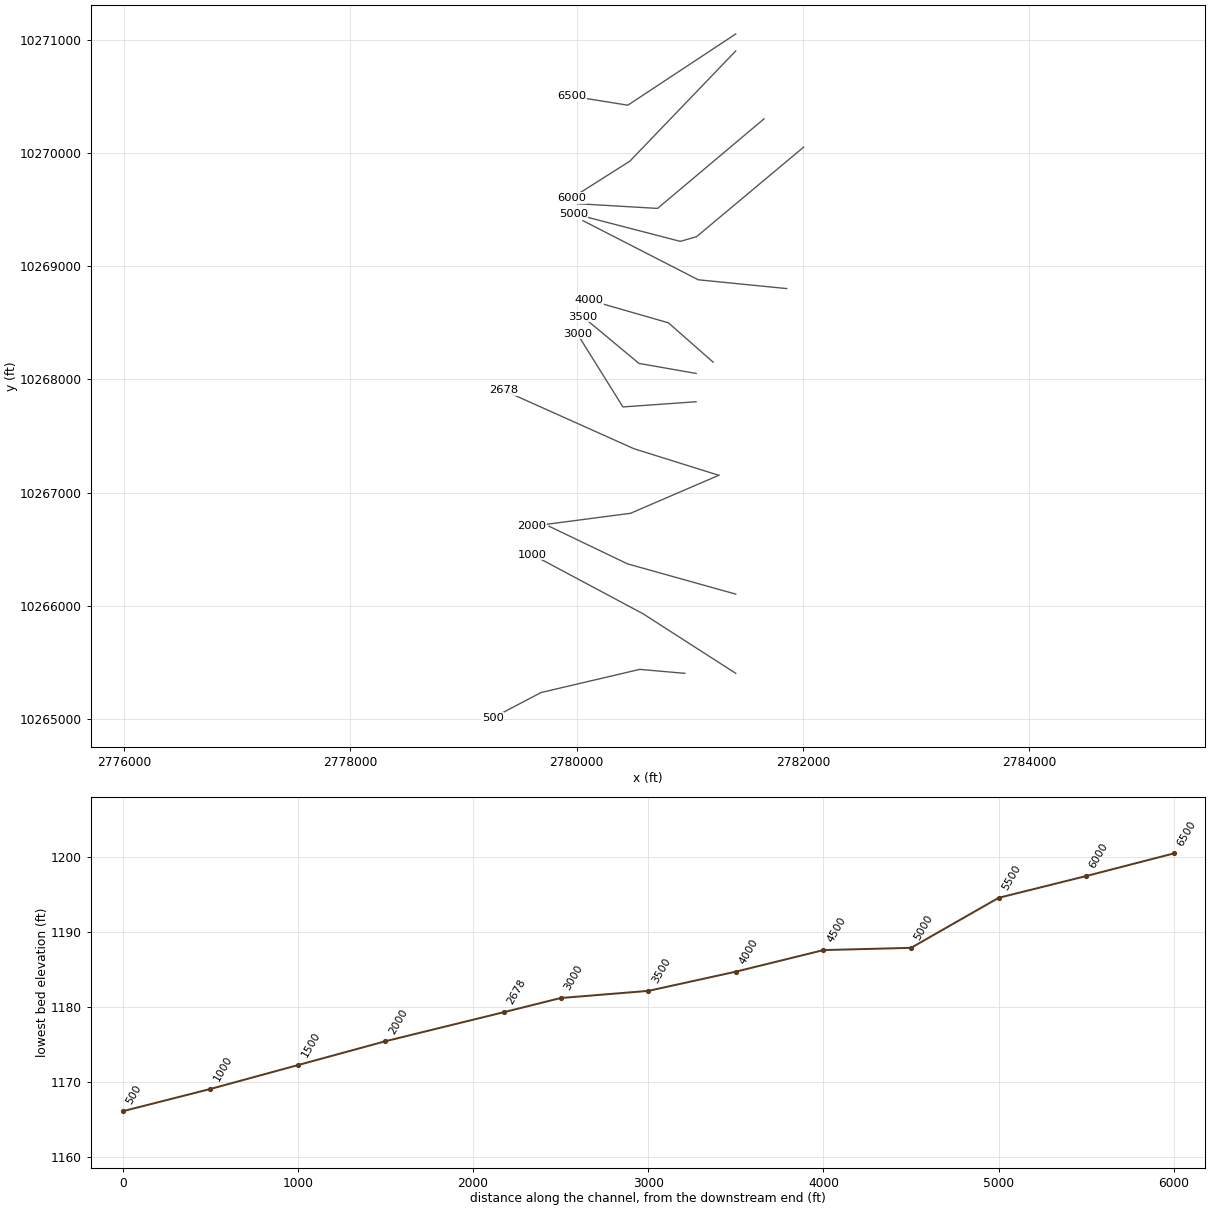
HEC-RAS study SANFERNANDO033.prj: SANFERNANDO033 Base Level Engineering

--- SANFERNANDO033.g01 (geometry) --- (continued)

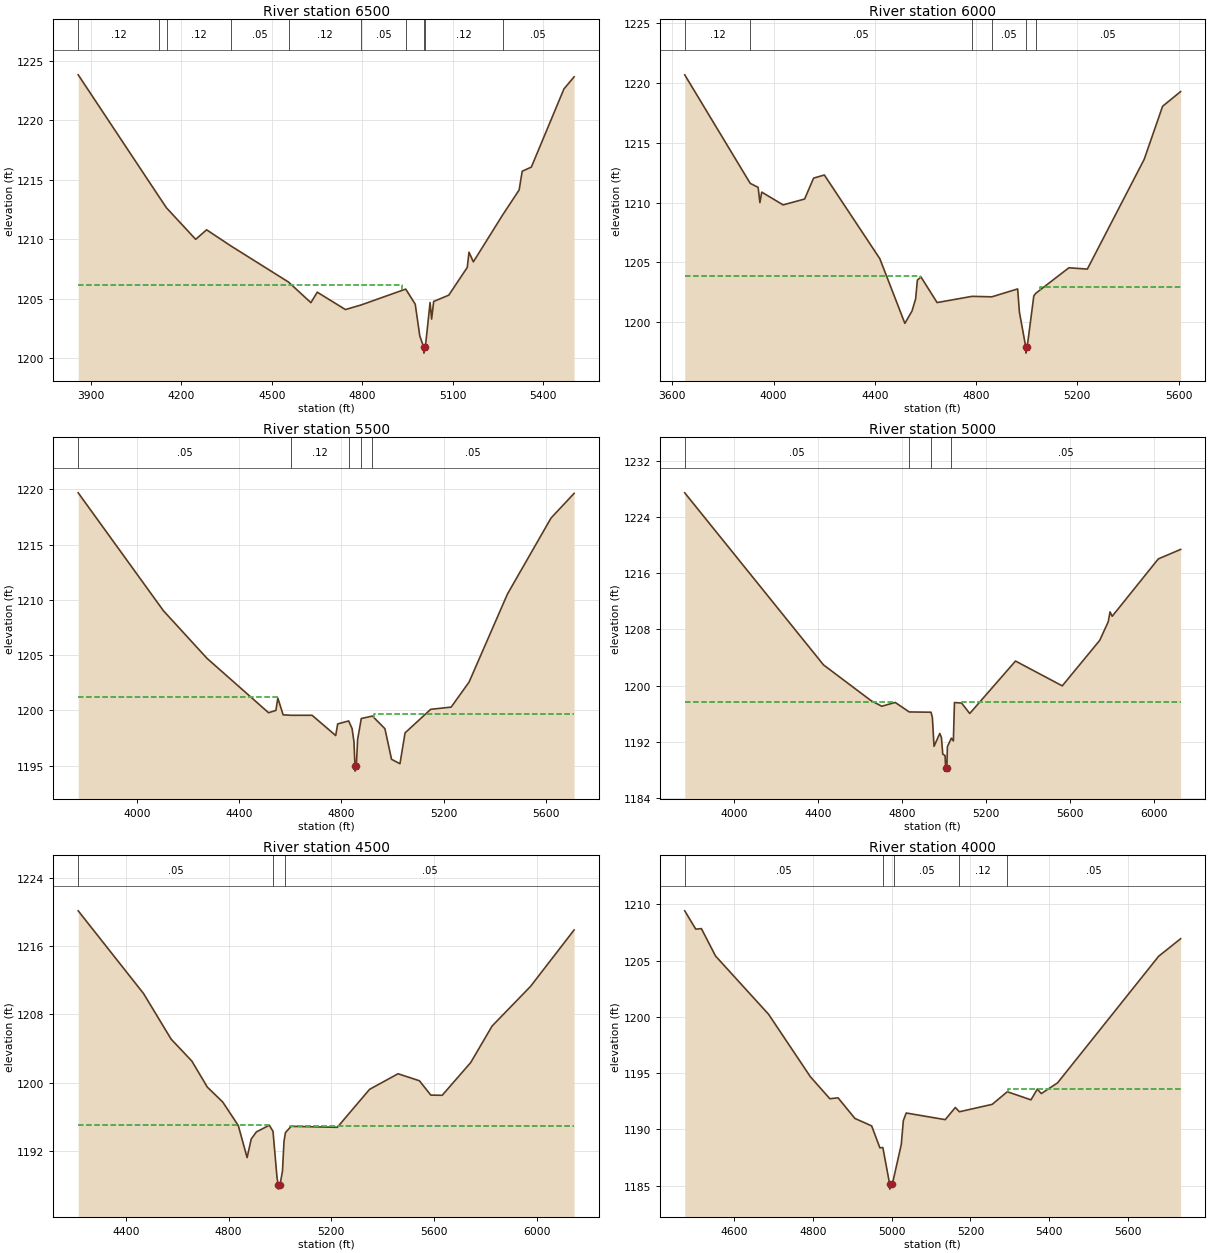
Type RM Length L Ch R = 1 ,6500    ,500,500,500
BEGIN DESCRIPTION:
SANFERNANDO033 13.0
END DESCRIPTION:
XS GIS Cut Line= 3
      2781405.69     10271053.11      2780452.25     10270423.62
      2779955.67     10270503.11
#Sta/Elev= 30
  3857.5  1223.8  4124.4 1213.61  4150.6 1212.62  4247.3 1209.98  4283.5 1210.78
  4364.5 1209.42  4555.3 1206.39  4629.6 1204.66  4650.7 1205.54  4744.2 1204.08
  4796.6 1204.47  4944.3  1205.8  4975.8 1204.53  4990.9 1201.87  5003.9 1200.92
  5004.4 1200.42  5009.3 1200.92  5025.1 1204.67  5030.2 1203.28    5037 1204.76
  5087.1 1205.29  5148.4 1207.62  5154.2  1208.9  5168.7 1208.09  5265.4 1212.01
  5320.6 1214.13  5330.7  1215.7  5361.1 1216.05  5469.3 1222.62  5502.9 1223.63
#Mann= 10 ,-1 , 0
  3857.5     .12       0  4124.4     .05       0  4150.6     .12       0
  4364.5     .05       0  4555.3     .12       0  4796.6     .05       0
  4944.3     .12       0  5003.9     .07       0  5009.3     .12       0
  5265.4     .05       0
#XS Ineff= 2 , 0
         4932.16 1206.13
Permanent Ineff=
       F       F
Bank Sta=5003.9,5009.3
XS Rating Curve= 0 ,0
Exp/Cntr=0.3,0.1

Type RM Length L Ch R = 1 ,6000    ,500,500,500
BEGIN DESCRIPTION:
SANFERNANDO033 12.0
END DESCRIPTION:
XS GIS Cut Line= 3
      2781405.66     10270903.08      2780469.45     10269928.64
       2779955.7     10269603.12
#Sta/Elev= 30
  3648.7 1220.69  3907.5 1211.61  3938.7 1211.28  3945.7    1210  3952.9 1210.88
  4037.5 1209.81  4122.4  1210.3  4157.9 1212.05  4200.4 1212.31  4419.6 1205.31
  4518.6  1199.9  4546.9 1200.94  4561.1 1201.95    4568 1203.52  4582.2 1203.78
    4646 1201.64  4784.2 1202.16  4862.3 1202.12  4964.2 1202.78  4971.2 1200.84
  4996.4 1197.91  4996.9 1197.41  5001.8 1197.91  5028.1  1202.2  5036.2 1202.42
  5166.7 1204.55  5239.6 1204.44  5464.2 1213.62    5537 1218.06  5608.2 1219.29
#Mann= 6 ,-1 , 0
  3648.7     .12       0  3907.5     .05       0  4784.2     .12       0
  4862.3     .05       0  4996.4     .07       0  5036.2     .05       0
#XS Ineff= 2 , 0
         4578.12 1203.82 5053.98         1202.93
Permanent Ineff=
       F       F
Bank Sta=4996.4,5001.8
XS Rating Curve= 0 ,0
Exp/Cntr=0.3,0.1

Type RM Length L Ch R = 1 ,5500    ,500,500,500
BEGIN DESCRIPTION:
SANFERNANDO033 11.0
END DESCRIPTION:
XS GIS Cut Line= 3
      2781655.65     10270303.08      2780714.52     10269511.45
      2780005.65     10269553.11
#Sta/Elev= 30
  3770.2 1219.68  4103.8 1209.01  4274.1 1204.71    4515 1199.79  4543.4    1200
  4551.2 1201.11    4572  1199.6  4602.7 1199.56  4685.2 1199.56  4777.5 1197.73
  4785.3 1198.78  4828.2 1199.05  4841.7 1198.35    4849 1197.15  4852.8 1195.01
  4853.3 1194.51  4858.3 1195.01  4863.3 1197.38  4877.6 1199.27  4921.2 1199.49
    4970 1198.35    4996 1195.58  5028.9 1195.18  5048.9 1197.97  5149.1  1200.1
  5229.2  1200.3  5299.4 1202.57  5449.5 1210.53  5619.9  1217.4  5710.1 1219.63
#Mann= 5 ,-1 , 0
  3770.2     .05       0  4602.7     .12       0  4828.2     .07       0
  4877.6     .12       0  4921.2     .05       0
#XS Ineff= 2 , 0
         4551.14 1201.21 4928.98         1199.68
Permanent Ineff=
       F       F
Bank Sta=4852.8,4858.3
XS Rating Curve= 0 ,0
Exp/Cntr=0.3,0.1

Type RM Length L Ch R = 1 ,5000    ,500,500,500
BEGIN DESCRIPTION:
SANFERNANDO033 10.0
END DESCRIPTION:
XS GIS Cut Line= 4
       2782005.7     10270053.13       2781058.8     10269261.38
       2780915.7     10269220.33      2779970.65     10269465.49
#Sta/Elev= 30
  3765.7 1227.44  4426.1 1202.96  4652.6 1197.87  4703.3 1197.08  4767.1 1197.62
    4834 1196.27  4937.6 1196.23  4944.1 1195.45  4951.9 1191.38  4979.2 1193.21
    4987 1192.65  4993.5 1190.27  5004.2 1190.07  5007.4 1188.35  5007.9 1187.85
  5012.9 1188.35  5015.4 1191.33  5034.4 1192.54  5043.9 1192.15  5049.1 1197.61
  5082.8 1197.54  5121.8 1196.05  5339.6 1203.51  5562.1 1199.98  5740.2 1206.45
  5780.7 1209.09  5789.4  1210.5  5799.7 1209.88    6019 1218.04  6125.2 1219.39
#Mann= 4 ,-1 , 0
  3765.7     .05       0    4834     .12       0  4937.6     .07       0
  5034.4     .05       0
#XS Ineff= 2 , 0
         4766.48 1197.74 5083.52         1197.62
Permanent Ineff=
       F       F
Bank Sta=5007.4,5012.9
XS Rating Curve= 0 ,0
Exp/Cntr=0.3,0.1

Type RM Length L Ch R = 1 ,4500    ,500,500,500
BEGIN DESCRIPTION:
SANFERNANDO033 9.0
END DESCRIPTION:
XS GIS Cut Line= 3
      2781855.73     10268803.11      2781074.29     10268880.86
      2780055.67     10269403.12
#Sta/Elev= 30
  4214.7 1220.14  4469.1 1210.45  4576.5 1205.11  4656.9 1202.55  4717.2  1199.5
  4777.5 1197.74  4837.8 1194.99  4872.1 1191.24  4888.1 1193.42  4908.2 1194.25
  4958.4 1195.03  4972.9 1194.32  4988.5  1188.9  4993.4 1188.05  4993.9 1187.55
  5000.1 1188.05  5009.7 1189.66  5015.6 1193.12  5021.2 1194.17  5043.4  1194.9
  5223.2 1194.79  5348.5 1199.23  5459.5 1201.06  5542.7 1200.24  5587.1 1198.56
  5631.5 1198.54  5742.5 1202.38  5825.6 1206.65  5975.4  1211.3  6144.7  1217.9
#Mann= 3 ,-1 , 0
  4214.7     .05       0  4972.9     .07       0  5021.2     .05       0
#XS Ineff= 2 , 0
         4957.39 1195.05 5039.77            1195
Permanent Ineff=
       F       F
Bank Sta=4993.4,5000.1
XS Rating Curve= 0 ,0
Exp/Cntr=0.3,0.1

Type RM Length L Ch R = 1 ,4000    ,500,500,500
BEGIN DESCRIPTION:
SANFERNANDO033 8.0
END DESCRIPTION:
XS GIS Cut Line= 3
      2781205.71     10268153.09      2780811.04     10268500.52
      2780105.66     10268703.12
#Sta/Elev= 30
  4474.2 1209.43  4502.2  1207.8  4516.5 1207.85  4552.5 1205.41  4687.2 1200.23
  4793.5 1194.67  4842.8 1192.72  4863.7  1192.8  4906.4 1190.97  4949.1  1190.3
    4970 1188.35  4977.5 1188.38  4994.5 1185.18    4995 1184.68  5001.8 1185.18
  5005.6 1185.75  5024.3 1188.65  5029.5 1190.77  5036.8 1191.45  5135.9 1190.86
  5161.6 1191.94    5172 1191.56  5255.3 1192.22  5293.6 1193.34  5353.8 1192.62
  5369.7 1193.57  5380.1 1193.18  5421.3 1194.13  5678.1 1205.39  5733.9 1206.95
#Mann= 5 ,-1 , 0
  4474.2     .05       0  4977.5     .07       0  5005.6     .05       0
    5172     .12       0  5293.6     .05       0
#XS Ineff= 2 , 0
                         5296.48         1193.57
Permanent Ineff=
       F       F
Bank Sta=4994.5,5001.8
XS Rating Curve= 0 ,0
Exp/Cntr=0.3,0.1

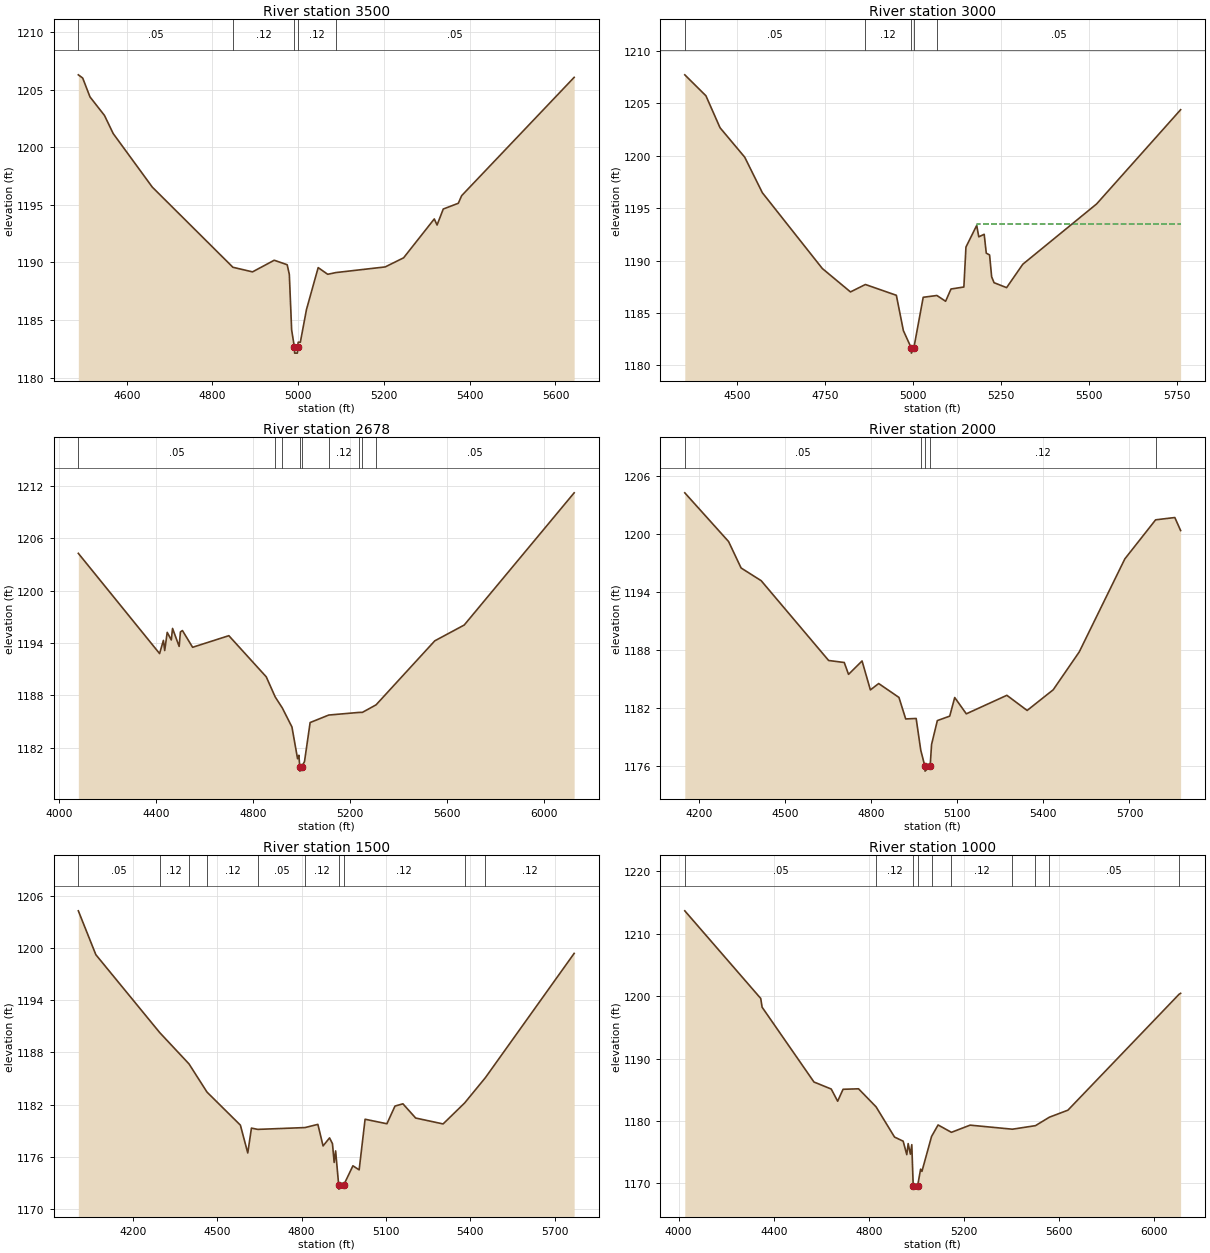
Type RM Length L Ch R = 1 ,3500    ,500,500,500
BEGIN DESCRIPTION:
SANFERNANDO033 7.0
END DESCRIPTION:
XS GIS Cut Line= 3
      2781055.72      10268053.1      2780550.64     10268141.73
      2780055.68     10268553.12
#Sta/Elev= 30
  4487.2  1206.3  4497.4 1206.02  4514.4 1204.38  4548.2 1202.77  4568.5  1201.2
  4659.8 1196.54  4847.7 1189.58  4893.4 1189.18  4944.1 1190.19  4974.3  1189.8
  4979.3 1188.96  4984.7 1184.14  4991.2 1182.62  4991.7 1182.12  4998.1 1182.12
  4998.6 1182.62    5000 1183.07    5005 1183.07  5019.3 1185.91  5046.6 1189.55
  5068.8 1188.97  5088.1 1189.12  5202.9 1189.61  5245.8  1190.4  5317.4 1193.78
  5323.9 1193.25  5338.3 1194.64  5373.4 1195.14  5381.2  1195.8  5643.6 1206.08
#Mann= 5 ,-1 , 0
  4487.2     .05       0  4847.7     .12       0  4991.2     .07       0
  4998.6     .12       0  5088.1     .05       0
Bank Sta=4991.2,4998.6
XS Rating Curve= 0 ,0
Exp/Cntr=0.3,0.1

Type RM Length L Ch R = 1 ,3000    ,322,322,322
BEGIN DESCRIPTION:
SANFERNANDO033 6.0
END DESCRIPTION:
XS GIS Cut Line= 3
      2781055.64     10267803.11      2780408.67     10267757.27
      2780005.71     10268403.07
#Sta/Elev= 30
  4351.4 1207.73  4411.5 1205.73  4451.6 1202.68  4521.8 1199.87  4571.9 1196.48
  4742.3 1189.25  4822.5 1187.01  4864.9 1187.72  4952.9 1186.69  4972.9 1183.32
  4995.2 1181.67  4995.7 1181.17  5002.7 1181.67  5029.3  1186.5  5068.2 1186.67
    5093 1186.12  5108.3 1187.29  5144.9 1187.48  5150.8 1191.29  5181.4 1193.36
  5187.3 1192.27  5202.7 1192.51  5208.6 1190.71    5218 1190.54  5223.9 1188.45
  5230.8 1187.89  5266.4 1187.42  5312.4 1189.65  5522.4 1195.41  5761.2  1204.4
#Mann= 5 ,-1 , 0
  4351.4     .05       0  4864.9     .12       0  4995.2     .07       0
  5002.7     .12       0  5068.2     .05       0
#XS Ineff= 2 , 0
                         5180.91         1193.46
Permanent Ineff=
       F       F
Bank Sta=4995.2,5002.7
XS Rating Curve= 0 ,0
Exp/Cntr=0.3,0.1

Type RM Length L Ch R = 1 ,2678    ,678,678,678
BEGIN DESCRIPTION:
SANFERNANDO033 5.0
END DESCRIPTION:
XS GIS Cut Line= 3
      2781255.68     10267153.11      2780505.76     10267388.06
      2779355.68     10267903.11
#Sta/Elev= 30
  4078.8 1204.27  4414.1 1192.78  4429.9 1194.29  4435.2 1193.13  4445.6 1195.21
  4462.4 1194.34  4467.6 1195.66  4494.8  1193.6  4500.1 1195.26  4508.4 1195.42
  4550.4  1193.5  4699.9 1194.83  4854.3 1190.11  4891.3  1187.8  4920.6 1186.54
  4960.3 1184.36  4983.5 1180.72  4988.9 1181.12  4992.4  1179.8  4992.9  1179.3
    5000  1179.8  5012.1 1180.39  5035.3 1184.87  5112.1 1185.73  5236.1 1186.03
  5251.2 1186.04  5307.4  1186.9  5549.7 1194.24  5671.1 1196.05  6124.8 1211.21
#Mann= 9 ,-1 , 0
  4078.8     .05       0  4891.3     .12       0  4920.6     .05       0
  4992.4     .05       0    5000     .05       0  5112.1     .12       0
  5236.1     .05       0  5251.2     .12       0  5307.4     .05       0
Bank Sta=4992.4,5000
XS Rating Curve= 0 ,0
Exp/Cntr=0.3,0.1

Type RM Length L Ch R = 1 ,2000    ,500,500,500
BEGIN DESCRIPTION:
SANFERNANDO033 4.0
END DESCRIPTION:
XS GIS Cut Line= 3
      2781255.71     10267153.12      2780476.32     10266817.44
       2779605.7     10266703.11
#Sta/Elev= 30
  4151.4 1204.27  4303.9 1199.22  4347.4 1196.48  4417.5 1195.16  4652.3 1186.89
  4706.7 1186.68  4721.6 1185.45  4768.7 1186.84  4797.7 1183.84  4826.6  1184.5
  4897.2 1183.06  4920.7 1180.83  4957.1 1180.88  4973.2 1177.58  4987.6 1175.92
  4988.1 1175.42  5005.9 1175.92  5010.7 1178.18  5030.9 1180.66    5074 1181.12
  5091.4 1183.05  5131.8 1181.36    5273 1183.28  5343.6 1181.71  5434.3 1183.85
  5525.1 1187.78  5683.8 1197.42    5791 1201.47  5857.9 1201.71  5878.1 1200.36
#Mann= 5 ,-1 , 0
  4151.4     .05       0  4973.2     .12       0  4987.6     .07       0
  5005.9     .12       0    5791     .05       0
Bank Sta=4987.6,5005.9
XS Rating Curve= 0 ,0
Exp/Cntr=0.3,0.1

Type RM Length L Ch R = 1 ,1500    ,500,500,500
BEGIN DESCRIPTION:
SANFERNANDO033 3.0
END DESCRIPTION:
XS GIS Cut Line= 3
      2781405.66     10266103.12      2780448.75     10266370.62
      2779755.68     10266703.11
#Sta/Elev= 30
  4006.4 1204.34  4068.7 1199.28  4295.8 1190.29  4399.6 1186.69  4463.8 1183.43
  4582.4 1179.62  4608.6 1176.41  4621.7 1179.28  4644.2 1179.13  4812.3 1179.34
  4857.8 1179.71  4876.3 1177.22  4899.3 1178.15  4909.7 1177.48  4915.7 1175.32
  4920.9 1176.65  4931.7 1172.74  4932.2 1172.24    4950 1172.74  4982.4 1174.93
  5004.5 1174.46  5025.6  1180.3  5103.2 1179.78  5131.9 1181.82  5160.1 1182.08
  5205.4 1180.44  5302.9 1179.76  5379.2 1182.17  5453.3  1185.1  5768.7 1199.43
#Mann= 10 ,-1 , 0
  4006.4     .05       0  4295.8     .12       0  4399.6     .05       0
  4463.8     .12       0  4644.2     .05       0  4812.3     .12       0
  4931.7     .07       0    4950     .12       0  5379.2     .05       0
  5453.3     .12       0
Bank Sta=4931.7,4950
XS Rating Curve= 0 ,0
Exp/Cntr=0.3,0.1

Type RM Length L Ch R = 1 ,1000    ,500,500,500
BEGIN DESCRIPTION:
SANFERNANDO033 2.0
END DESCRIPTION:
XS GIS Cut Line= 3
      2781405.72     10265403.09      2780586.12     10265929.72
      2779605.68     10266453.11
#Sta/Elev= 30
  4025.8 1213.69  4345.2 1199.64  4351.1 1198.23  4569.1 1186.24  4641.8 1185.11
  4668.8 1183.16  4691.5 1185.07  4756.7 1185.15  4830.5 1182.25    4908 1177.41
  4944.3 1176.75  4959.5 1174.59  4965.4 1176.36  4974.7 1174.67  4980.6 1176.19
  4986.6 1169.56  4987.1 1169.06    5005 1169.56  5017.7 1172.26  5023.3 1171.91
  5063.7  1177.5  5091.2 1179.35  5147.3 1178.17  5225.9 1179.32  5403.9 1178.67
  5500.8 1179.24  5559.6  1180.6  5637.3 1181.72  6104.9 1200.31  6111.4 1200.46
#Mann= 10 ,-1 , 0
  4025.8     .05       0  4830.5     .12       0  4986.6     .07       0
    5005     .12       0  5063.7     .05       0  5147.3     .12       0
  5403.9     .05       0  5500.8     .12       0  5559.6     .05       0
  6104.9     .12       0
Bank Sta=4986.6,5005
XS Rating Curve= 0 ,0
Exp/Cntr=0.3,0.1

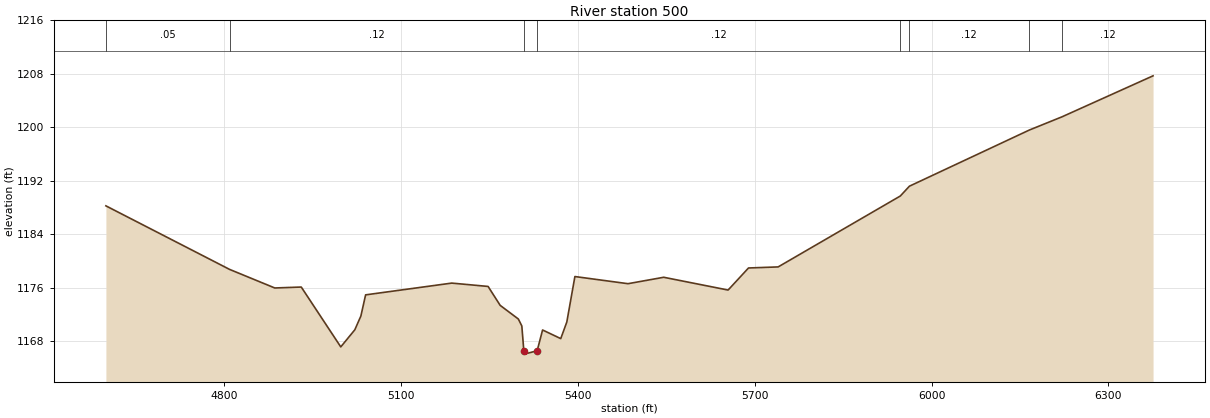
Type RM Length L Ch R = 1 ,500     ,0,0,0
BEGIN DESCRIPTION:
SANFERNANDO033 1.0
END DESCRIPTION:
XS GIS Cut Line= 4
      2780955.69     10265403.11      2780557.21     10265437.98
      2779686.05     10265233.68      2779260.02     10265010.59
#Sta/Elev= 30
    4600 1188.27  4809.7 1178.77  4886.4 1175.99  4931.3 1176.13  4998.3 1167.18
  5022.1 1169.74  5032.4  1171.8  5040.4 1174.96  5186.5 1176.72  5248.1 1176.22
  5268.6 1173.39  5299.4 1171.35  5305.3 1170.31  5308.7  1166.6  5309.2  1166.1
  5331.3  1166.6  5340.5 1169.71  5371.3 1168.42  5381.6  1170.9  5395.3  1177.7
  5485.3 1176.63  5545.9 1177.59  5655.1 1175.68  5689.7 1178.98    5740 1179.14
  5947.1 1189.74  5962.6 1191.21  6165.8  1199.6  6221.3 1201.58  6375.7 1207.71
#Mann= 8 ,-1 , 0
    4600     .05       0  4809.7     .12       0  5308.7     .07       0
  5331.3     .12       0  5947.1     .05       0  5962.6     .12       0
  6165.8     .05       0  6221.3     .12       0
Bank Sta=5308.7,5331.3
XS Rating Curve= 0 ,0
Exp/Cntr=0.3,0.1

Chan Stop Cuts=-1
Use User Specified Reach Order=0
Composite Channel Slope=5