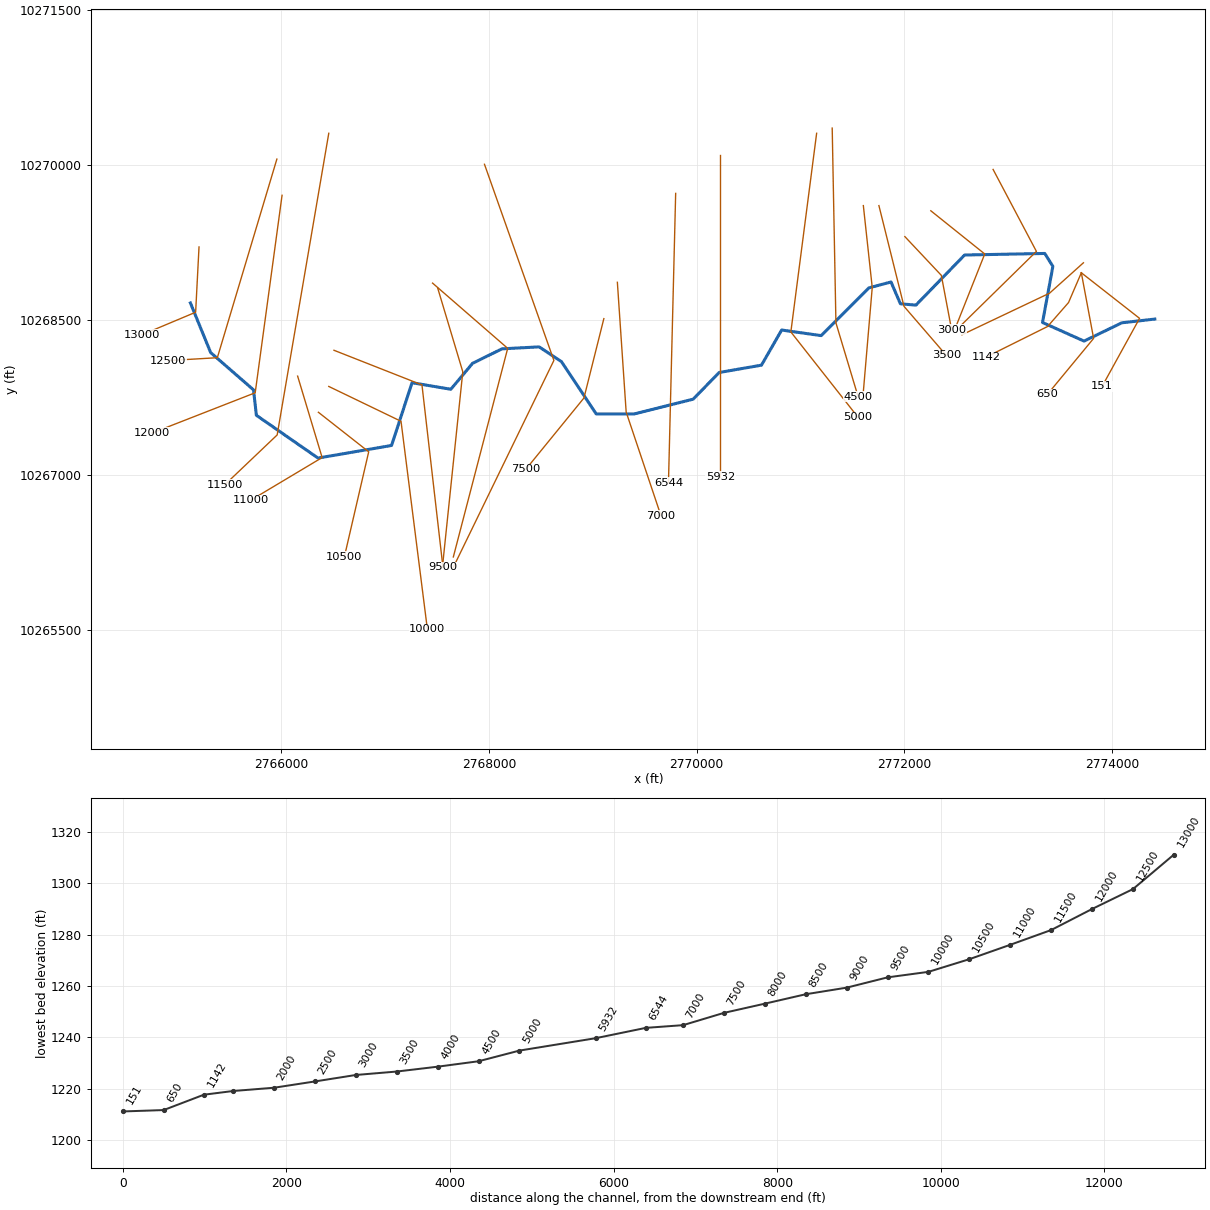
--- SANFERNANDO035.prj (project) ---

Proj Title=SANFERNANDO035 Base Level Engineering
Current Plan=p01
Default Exp/Contr=0.3,0.1
English Units
Geom File=g01
Flow File=f01
Plan File=p01
Y Axis Title=Elevation
X Axis Title(PF)=Main Channel Distance
X Axis Title(XS)=Station
BEGIN DESCRIPTION:
SANFERNANDO035
END DESCRIPTION:
DSS Export Rating Curves= 0
DSS Export Rating Curve Sorted= 0
DSS Export Volume Flow Curves= 0
DXF OffsetX= 0
DXF OffsetY= 0
DXF ScaleX= 1
DXF ScaleY= 10

--- SANFERNANDO035.p01 (plan) ---

Plan Title=Multiple Run
Short Identifier=Multiple
Geom File=g01
Flow File=f01
Subcritical Flow
K Sum by GR= 0
Std Step Tol= 0.01
Critical Tol= 0.01
Num of Std Step Trials= 20
Max Error Tol= 0.3
Flow Tol Ratio= 0.001
Split Flow NTrial= 30
Split Flow Tol= 0.02
Split Flow Ratio= 0.02
Log Output Level= 0
Friction Slope Method= 1
Unsteady Friction Slope Method= 2
Unsteady Bridges Friction Slope Method= 1
Parabolic Critical Depth
Global Vel Dist=  1 , 1 , 1
Global Log Level= 0
CheckData=True
Encroach Param= -1, 0, 0, 0
BEGIN DESCRIPTION:
Multiple Run
END DESCRIPTION:

--- SANFERNANDO035.f01 (steady flow) ---

Flow Title=Multiple
Number of Profiles=7
Profile Names=10-year,25-year,50-year,1pct_min,100-year,1pct_plu,500-year
River Rch & RM= SANFERNANDO035,Reach-1,13000
     376     599     757     442     992    2228    1342
River Rch & RM= SANFERNANDO035,Reach-1,5000
     636    1053    1275     771    1692    3714    2275
Boundary for River Rch & Prof#=SANFERNANDO035,Reach-1,1
Up Type=0
Dn Type=3
Dn Slope=0.005
Boundary for River Rch & Prof#=SANFERNANDO035,Reach-1,2
Up Type=0
Dn Type=3
Dn Slope=0.005
Boundary for River Rch & Prof#=SANFERNANDO035,Reach-1,3
Up Type=0
Dn Type=3
Dn Slope=0.005
Boundary for River Rch & Prof#=SANFERNANDO035,Reach-1,4
Up Type=0
Dn Type=3
Dn Slope=0.005
Boundary for River Rch & Prof#=SANFERNANDO035,Reach-1,5
Up Type=0
Dn Type=3
Dn Slope=0.005
Boundary for River Rch & Prof#=SANFERNANDO035,Reach-1,6
Up Type=0
Dn Type=3
Dn Slope=0.005
Boundary for River Rch & Prof#=SANFERNANDO035,Reach-1,7
Up Type=0
Dn Type=3
Dn Slope=0.005

--- SANFERNANDO035.g01 (geometry) ---

Geom Title=Existing Conditions
Program Version=4.10

River Reach=SANFERNANDO035  ,Reach-1
Reach XY= 30
      2765122.75       10268661.      2765317.75       10268181.
      2765730.75       10267820.      2765758.25       10267574.
        2766352.       10267160.       2767060.5       10267282.
      2767257.75       10267889.      2767631.75       10267826.
      2767841.25       10268077.      2768124.25       10268217.
        2768482.       10268236.       2768697.5       10268093.
      2769032.25       10267587.      2769397.75       10267587.
       2769966.5       10267730.      2770216.25       10267988.
      2770624.25       10268059.      2770818.75       10268399.
        2771199.       10268345.        2771659.       10268807.
       2771872.5       10268864.      2771962.75       10268653.
      2772112.25       10268640.        2772581.       10269125.
       2773353.5       10269140.       2773431.5       10269015.
      2773331.75       10268472.        2773732.       10268292.
      2774095.75       10268469.      2774413.25       10268505.

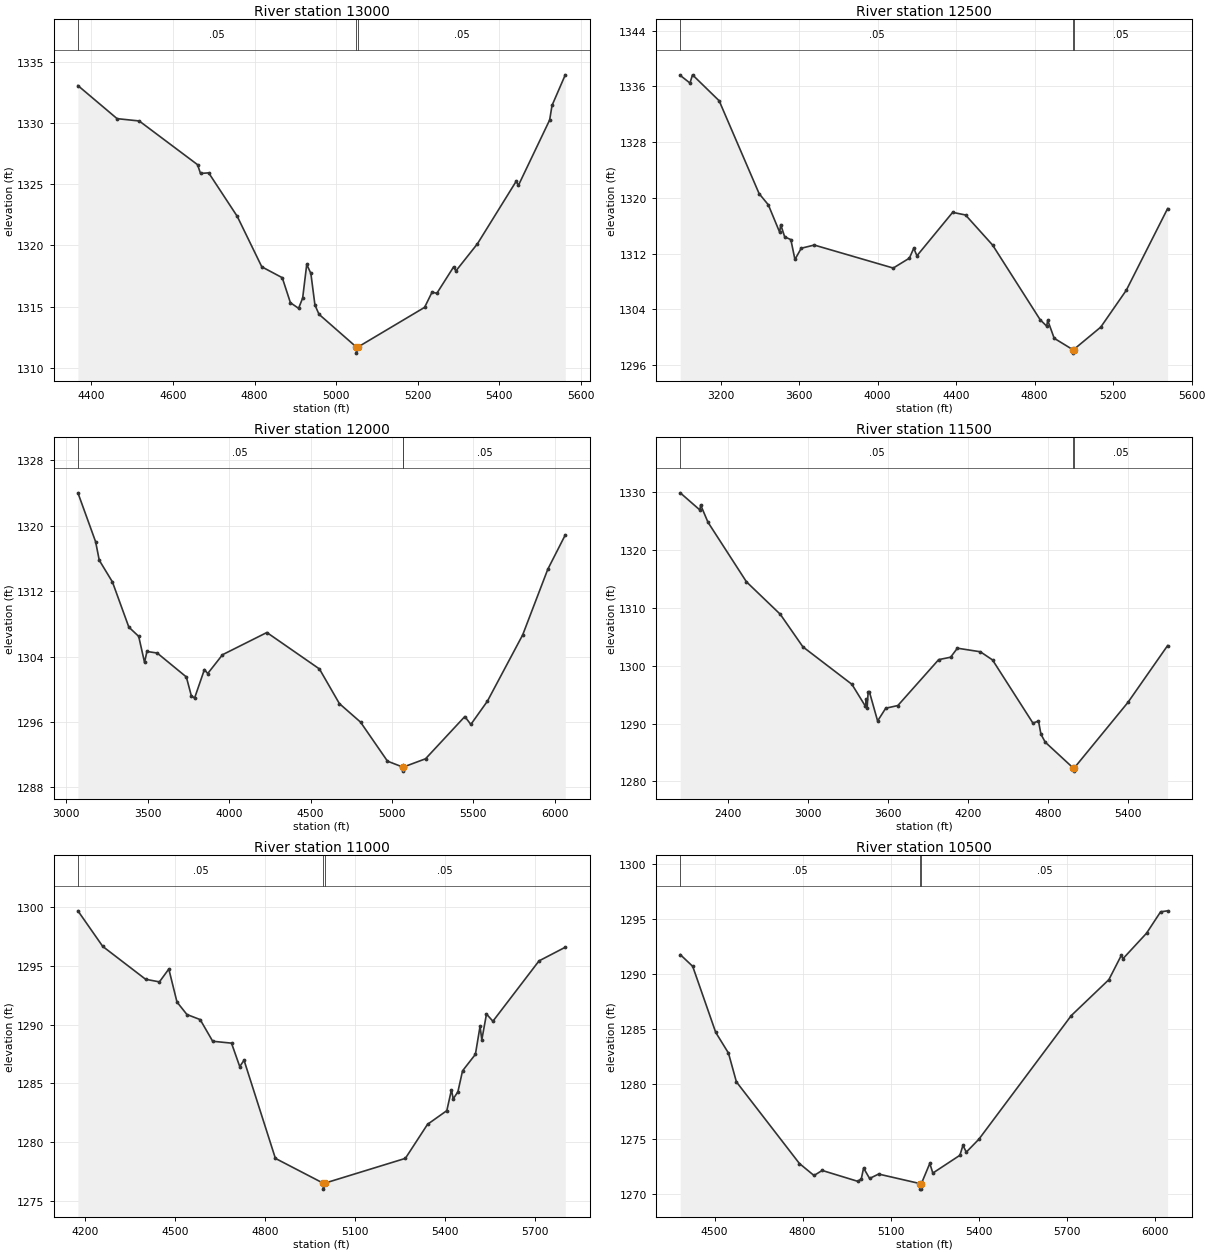
Type RM Length L Ch R = 1 ,13000   ,500,500,500
BEGIN DESCRIPTION:
SANFERNANDO035 26.0
END DESCRIPTION:
XS GIS Cut Line= 3
      2765205.68     10269203.11      2765173.04     10268571.16
      2764655.71     10268353.12
#Sta/Elev= 30
  4367.2  1333.1  4463.2 1330.39  4517.4  1330.2  4660.3 1326.62  4667.6  1325.9
  4687.6 1325.95  4757.7 1322.38  4817.8 1318.25  4867.9 1317.36  4887.9 1315.31
  4907.9 1314.85  4917.9 1315.69  4927.9 1318.45    4938 1317.71    4948 1315.12
    4958 1314.36  5049.4 1311.68  5049.6 1311.18  5053.4 1311.68  5216.7 1314.93
    5235 1316.18  5246.7 1316.08  5287.9 1318.25  5293.3 1317.91  5346.2 1320.14
  5441.1 1325.26  5446.5 1324.92  5523.1 1330.28  5528.9 1331.47  5561.4 1333.98
#Mann= 3 ,-1 , 0
  4367.2     .05       0  5049.4     .03       0  5053.4     .05       0
Bank Sta=5049.4,5053.4
XS Rating Curve= 0 ,0
Exp/Cntr=0.3,0.1

Type RM Length L Ch R = 1 ,12500   ,500,500,500
BEGIN DESCRIPTION:
SANFERNANDO035 25.0
END DESCRIPTION:
XS GIS Cut Line= 3
      2765955.69     10270053.14      2765382.21     10268131.17
      2764905.64     10268103.11
#Sta/Elev= 30
  2994.3 1337.57    3044 1336.47  3056.9 1337.65  3192.6 1333.93  3396.3 1320.61
  3443.1 1319.01    3501 1315.07  3506.2 1316.17  3526.5 1314.41  3557.9 1314.02
  3578.7 1311.17  3610.8 1312.78  3677.1 1313.24  4079.6 1309.94  4161.9 1311.36
    4184 1312.79  4200.3  1311.7  4382.3 1317.93  4447.9 1317.55  4585.7 1313.24
  4828.1 1302.53  4861.3 1301.61  4866.5 1302.45  4899.6 1299.87  4994.4 1298.24
  4994.6 1297.74  4998.4 1298.24  5136.8 1301.47    5267 1306.76  5477.4 1318.47
#Mann= 3 ,-1 , 0
  2994.3     .05       0  4994.4     .05       0  4998.4     .05       0
Bank Sta=4994.4,4998.4
XS Rating Curve= 0 ,0
Exp/Cntr=0.3,0.1

Type RM Length L Ch R = 1 ,12000   ,500,500,500
BEGIN DESCRIPTION:
SANFERNANDO035 24.0
END DESCRIPTION:
XS GIS Cut Line= 3
      2766005.68     10269703.08      2765746.93     10267792.02
      2764755.69     10267403.11
#Sta/Elev= 30
  3071.5 1324.03  3180.3 1318.04  3202.7 1315.78  3283.4 1313.13  3384.3  1307.6
  3444.8 1306.47  3480.8 1303.28  3495.3 1304.62  3558.4 1304.43  3737.5  1301.5
  3767.8 1299.22  3787.9 1298.91  3848.5 1302.41  3868.7 1301.92  3959.5 1304.22
    4232 1306.94  4554.9 1302.48  4677.5 1298.24  4807.2 1295.98  4972.8  1291.2
  5066.3 1290.48  5066.6 1289.98  5070.3 1290.48  5206.6 1291.49  5447.9 1296.66
  5484.7 1295.69  5586.2 1298.53  5803.2 1306.65  5957.4 1314.68  6064.8 1318.88
#Mann= 3 ,-1 , 0
  3071.5     .05       0  5066.3     .03       0  5070.3     .05       0
Bank Sta=5066.3,5070.3
XS Rating Curve= 0 ,0
Exp/Cntr=0.3,0.1

Type RM Length L Ch R = 1 ,11500   ,500,500,500
BEGIN DESCRIPTION:
SANFERNANDO035 23.0
END DESCRIPTION:
XS GIS Cut Line= 3
      2766455.68     10270303.08      2765958.54     10267383.91
       2765455.7     10266903.12
#Sta/Elev= 30
  2038.8 1329.93  2186.8 1326.95  2191.8 1327.84    2247 1324.84  2535.8 1314.53
  2789.4 1308.92  2959.4 1303.28    3327  1296.8  3428.5    1293    3436 1294.28
  3441.1 1292.72  3448.8 1295.47  3458.9 1295.44  3519.8 1290.46  3580.6 1292.66
  3671.8 1293.13    3978 1301.07  4067.6 1301.49  4118.3 1303.05  4290.7 1302.43
    4382 1301.02  4685.3 1290.09  4726.9 1290.45  4745.5 1288.16  4777.6 1286.79
  4989.5 1282.28  4989.7 1281.78  4993.5 1282.28  5398.7 1293.69  5695.7  1303.5
#Mann= 3 ,-1 , 0
  2038.8     .05       0  4989.5     .03       0  4993.5     .05       0
Bank Sta=4989.5,4993.5
XS Rating Curve= 0 ,0
Exp/Cntr=0.3,0.1

Type RM Length L Ch R = 1 ,11000   ,500,500,500
BEGIN DESCRIPTION:
SANFERNANDO035 22.0
END DESCRIPTION:
XS GIS Cut Line= 3
      2766155.69     10267953.08      2766391.72     10267164.97
      2765705.66      10266753.1
#Sta/Elev= 30
  4177.3 1299.65    4260 1296.63  4402.8 1293.84  4448.7 1293.62    4480 1294.71
  4507.2 1291.91  4540.3 1290.85  4584.4 1290.42  4626.1 1288.58  4688.8 1288.42
  4716.2 1286.43  4730.5 1286.97  4834.9 1278.64  4994.5 1276.53  4994.8 1276.03
  4998.5 1276.53  5267.7 1278.64  5341.5 1281.53  5405.7 1282.69  5421.2 1284.46
    5427 1283.69  5442.6 1284.29  5458.1 1286.07  5500.9 1287.47  5516.4 1289.85
  5522.3 1288.71  5537.8 1290.89  5559.2 1290.28  5712.7  1295.4  5800.2 1296.56
#Mann= 3 ,-1 , 0
  4177.3     .05       0  4994.5     .03       0  4998.5     .05       0
Bank Sta=4994.5,4998.5
XS Rating Curve= 0 ,0
Exp/Cntr=0.3,0.1

Type RM Length L Ch R = 1 ,10500   ,500,500,500
BEGIN DESCRIPTION:
SANFERNANDO035 21.0
END DESCRIPTION:
XS GIS Cut Line= 3
       2766355.7      10267603.1      2766840.31     10267220.73
      2766605.69     10266203.13
#Sta/Elev= 30
  4382.7 1291.76  4425.2 1290.69  4503.7 1284.68  4547.1  1282.8  4574.2 1280.18
  4789.1 1272.75  4838.8 1271.66  4866.7 1272.12  4987.9 1271.13    5000 1271.35
  5007.8 1272.34  5028.3 1271.39  5059.1 1271.79  5200.8 1270.92  5201.1 1270.42
  5204.6 1270.42  5204.8 1270.92  5233.6 1272.76  5243.9 1271.88  5336.2  1273.5
  5346.5  1274.4  5358.1 1273.79  5400.9 1274.96  5715.9 1286.21  5844.1 1289.48
  5886.9 1291.71    5892 1291.38  5972.4  1293.7  6020.4 1295.65  6044.3 1295.74
#Mann= 3 ,-1 , 0
  4382.7     .05       0  5200.8     .05       0  5204.8     .05       0
Bank Sta=5200.8,5204.8
XS Rating Curve= 0 ,0
Exp/Cntr=0.3,0.1

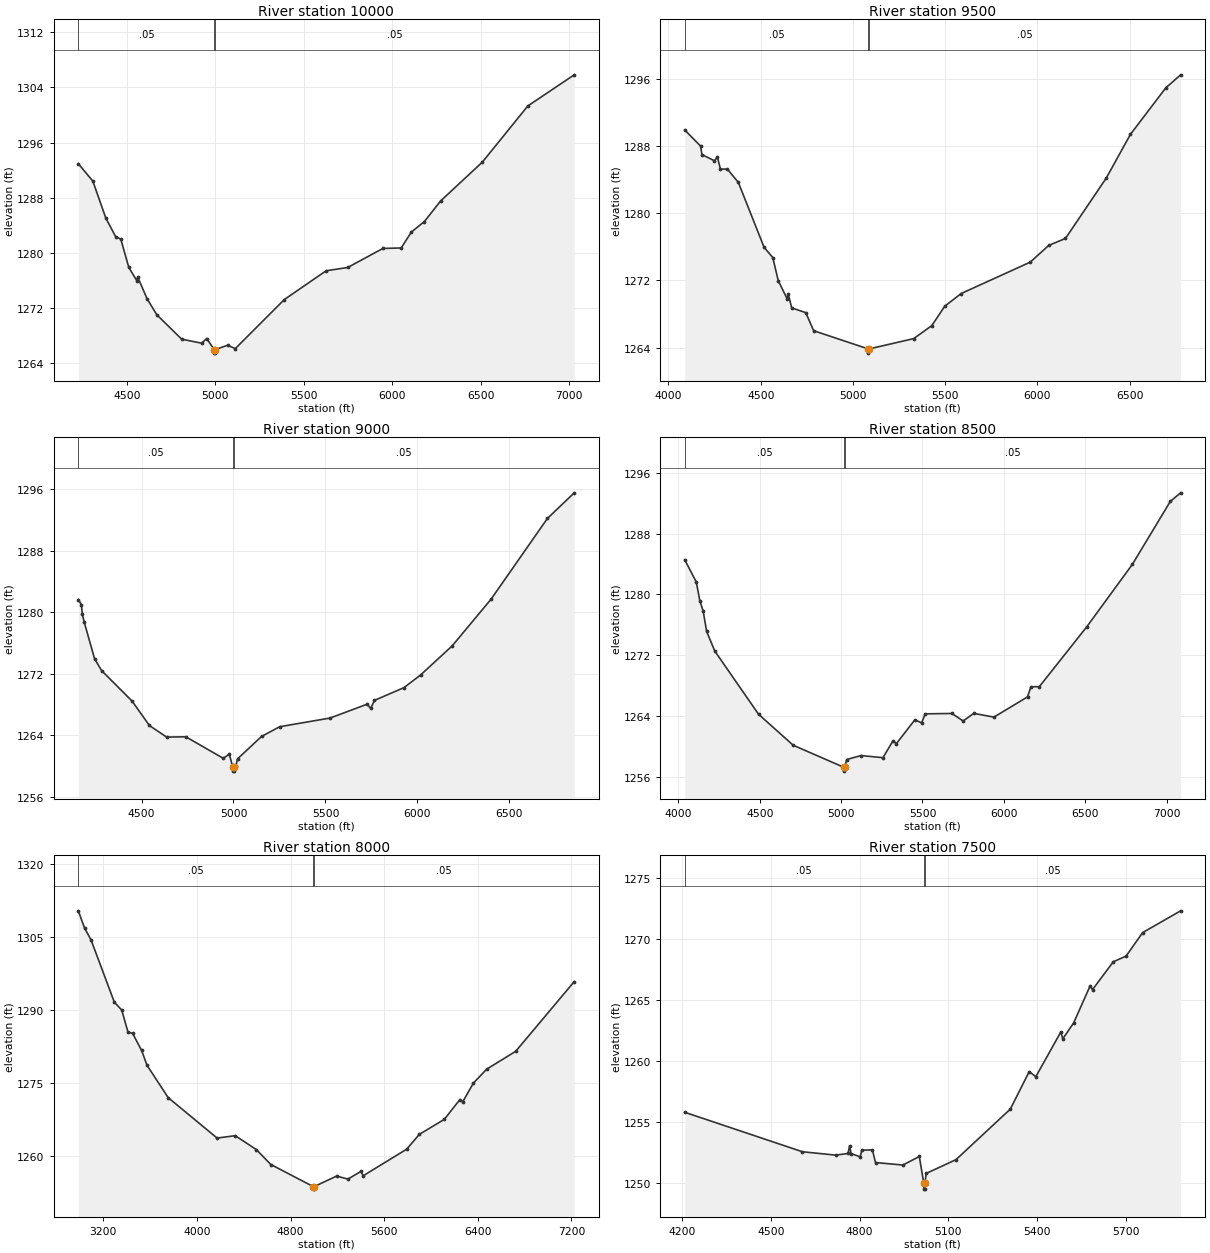
Type RM Length L Ch R = 1 ,10000   ,500,500,500
BEGIN DESCRIPTION:
SANFERNANDO035 20.0
END DESCRIPTION:
XS GIS Cut Line= 3
       2766455.7      10267853.1      2767151.75     10267515.96
      2767405.68     10265503.12
#Sta/Elev= 30
  4226.6 1292.93  4308.4 1290.41  4382.1 1285.04  4437.7 1282.34  4466.5 1282.01
  4511.6 1277.91  4556.8 1275.99  4562.3 1276.49  4615.5 1273.34  4669.7 1271.05
  4810.7  1267.5  4923.6 1266.92  4951.8 1267.59  4994.9 1265.98  4995.2 1265.48
  4998.7 1265.48  4998.9 1265.98  5069.9 1266.62  5113.7 1266.14  5390.9 1273.25
  5626.7 1277.41  5748.7 1277.89  5947.7 1280.65  6051.1 1280.72  6108.3 1283.02
  6182.1 1284.55  6273.8 1287.53  6509.6 1293.16  6766.7  1301.3  7028.8 1305.81
#Mann= 3 ,-1 , 0
  4226.6     .05       0  4994.9     .03       0  4998.9     .05       0
Bank Sta=4994.9,4998.9
XS Rating Curve= 0 ,0
Exp/Cntr=0.3,0.1

Type RM Length L Ch R = 1 ,9500    ,500,500,500
BEGIN DESCRIPTION:
SANFERNANDO035 19.0
END DESCRIPTION:
XS GIS Cut Line= 3
       2766505.7     10268203.11      2767353.51     10267867.83
      2767555.69     10266103.08
#Sta/Elev= 30
  4088.3 1289.94  4174.3 1288.02  4181.6 1287.01  4249.6 1286.27  4265.4 1286.72
  4281.8 1285.27  4319.5 1285.28  4378.9 1283.69  4518.4 1275.95  4565.5 1274.73
  4595.2 1271.98  4643.9 1269.78  4649.3 1270.37  4668.3 1268.72  4744.2 1268.16
  4787.3    1266  5083.3 1263.83  5083.5 1263.33  5087.3 1263.83  5329.2 1265.06
  5427.5 1266.61  5497.6 1268.92  5586.8 1270.44    5961 1274.18  6061.6 1276.18
  6152.2 1277.01  6373.6 1284.22  6504.5 1289.43  6695.7 1294.96  6776.3 1296.52
#Mann= 3 ,-1 , 0
  4088.3     .05       0  5083.3     .03       0  5087.3     .05       0
Bank Sta=5083.3,5087.3
XS Rating Curve= 0 ,0
Exp/Cntr=0.3,0.1

Type RM Length L Ch R = 1 ,9000    ,500,500,500
BEGIN DESCRIPTION:
SANFERNANDO035 18.0
END DESCRIPTION:
XS GIS Cut Line= 3
      2767505.68     10268803.14      2767746.85     10267995.06
      2767555.69     10266153.16
#Sta/Elev= 30
  4156.7 1281.65  4173.3 1281.01  4178.5 1279.72    4188 1278.78  4244.8 1273.96
  4283.1 1272.41  4448.8 1268.44  4542.9 1265.26  4636.8 1263.75  4741.1 1263.79
  4944.1 1260.99  4977.2 1261.53  4996.4 1259.82  4996.7 1259.32  5000.2 1259.32
  5000.4 1259.82    5012 1259.95  5022.1 1260.92  5152.2 1263.83  5250.9  1265.1
  5524.8 1266.23  5725.8 1268.03  5745.9 1267.48    5766 1268.53  5926.7 1270.19
  6017.4 1271.85  6188.3 1275.62  6399.4 1281.69  6706.3 1292.22  6851.8 1295.55
#Mann= 3 ,-1 , 0
  4156.7     .05       0  4996.4     .05       0  5000.4     .05       0
Bank Sta=4996.4,5000.4
XS Rating Curve= 0 ,0
Exp/Cntr=0.3,0.1

Type RM Length L Ch R = 1 ,8500    ,500,500,500
BEGIN DESCRIPTION:
SANFERNANDO035 17.0
END DESCRIPTION:
XS GIS Cut Line= 3
      2767455.66     10268853.13      2768179.47     10268221.89
      2767655.69     10266203.13
#Sta/Elev= 30
  4039.6 1284.57  4110.4 1281.65  4132.2 1279.19  4153.1  1277.8    4174 1275.14
  4224.3 1272.55  4492.9 1264.24  4705.6 1260.16  5017.4 1257.25  5017.6 1256.75
  5021.4 1257.25  5034.9 1258.28  5122.7  1258.8    5257 1258.52    5319 1260.74
  5339.7 1260.37  5453.3 1263.51  5494.6  1263.1  5516.6 1264.29  5680.6 1264.34
  5749.7 1263.35  5814.9 1264.35  5938.9 1263.86  6145.1 1266.52  6166.1 1267.85
  6217.8 1267.87  6510.2 1275.78  6789.1 1283.96  7022.2 1292.25  7085.6 1293.38
#Mann= 3 ,-1 , 0
  4039.6     .05       0  5017.4     .03       0  5021.4     .05       0
Bank Sta=5017.4,5021.4
XS Rating Curve= 0 ,0
Exp/Cntr=0.3,0.1

Type RM Length L Ch R = 1 ,8000    ,500,500,500
BEGIN DESCRIPTION:
SANFERNANDO035 16.0
END DESCRIPTION:
XS GIS Cut Line= 3
       2767955.7     10270003.07      2768624.34     10268104.68
       2767655.7     10266103.14
#Sta/Elev= 30
  2987.3 1310.41  3040.3 1306.87  3095.6 1304.43  3294.7  1291.6  3358.3 1289.96
  3411.3 1285.44  3451.1 1285.17    3528 1281.64    3575 1278.55  3755.4 1271.92
  4172.8  1263.6  4327.6 1264.09    4508 1261.23  4631.8 1258.15  4996.2 1253.58
  4996.4 1253.08  5000.2 1253.58  5194.1 1255.77  5290.6 1255.15  5402.9 1256.75
    5420 1255.82  5792.5 1261.31  5899.9 1264.35  6114.3 1267.46  6244.2 1271.45
  6272.4 1271.11  6362.7 1274.94  6475.7 1277.79  6723.7 1281.47  7223.6 1295.83
#Mann= 3 ,-1 , 0
  2987.3     .05       0  4996.2     .05       0  5000.2     .05       0
Bank Sta=4996.2,5000.2
XS Rating Curve= 0 ,0
Exp/Cntr=0.3,0.1

Type RM Length L Ch R = 1 ,7500    ,500,500,500
BEGIN DESCRIPTION:
SANFERNANDO035 15.0
END DESCRIPTION:
XS GIS Cut Line= 3
      2769105.75     10268509.29      2768914.04     10267741.46
      2768355.71     10267053.14
#Sta/Elev= 30
  4208.6  1255.8  4606.6 1252.56  4719.9 1252.28  4761.1 1252.42  4766.3 1253.05
  4771.5 1252.41  4802.4 1252.14  4807.5 1252.69  4843.6 1252.71    4854 1251.67
  4946.8 1251.47  5002.2 1252.17  5017.2 1249.99  5017.5 1249.49    5021 1249.49
  5021.2 1249.99  5025.6 1250.78  5126.3 1251.91  5310.1 1256.06  5374.1 1259.14
  5396.4 1258.72  5481.1  1262.4  5487.6 1261.83  5524.3 1263.13  5580.3 1266.19
  5588.2 1265.87  5658.6 1268.16  5701.7 1268.62  5757.7 1270.55  5886.3 1272.34
#Mann= 3 ,-1 , 0
  4208.6     .05       0  5017.2     .03       0  5021.2     .05       0
Bank Sta=5017.2,5021.2
XS Rating Curve= 0 ,0
Exp/Cntr=0.3,0.1

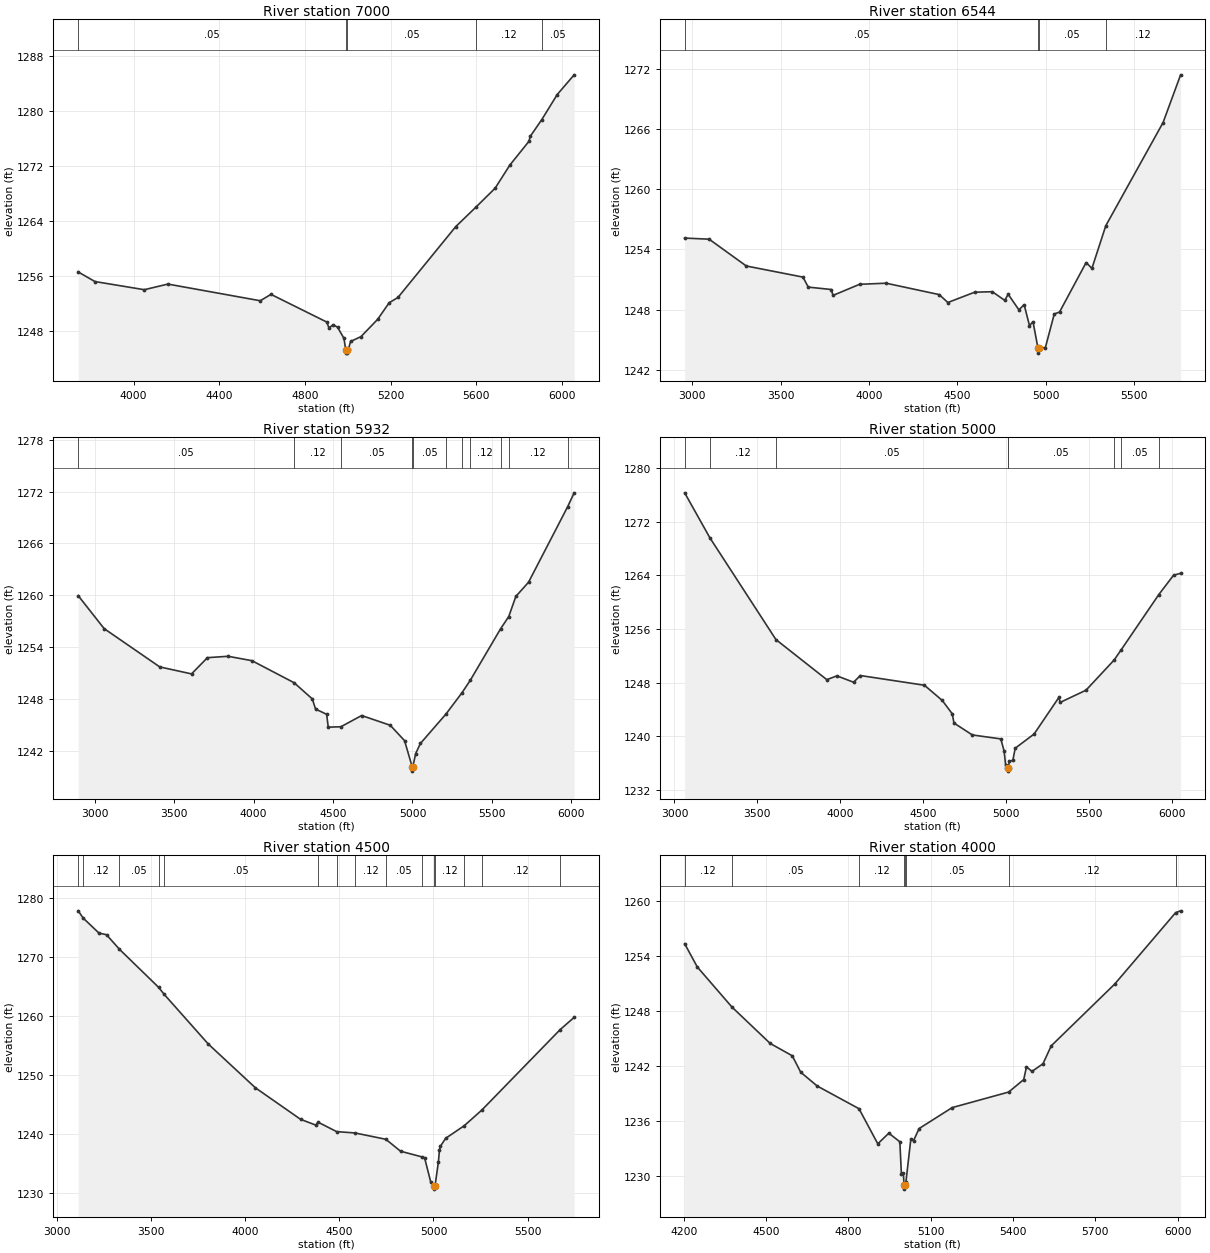
Type RM Length L Ch R = 1 ,7000    ,456,456,456
BEGIN DESCRIPTION:
SANFERNANDO035 14.0
END DESCRIPTION:
XS GIS Cut Line= 3
      2769235.96     10268860.89       2769320.7     10267605.35
      2769655.67     10266603.14
#Sta/Elev= 30
  3741.6 1256.54  3819.6 1255.14  4050.1 1253.95  4160.3 1254.77  4591.3 1252.34
  4641.4 1253.27    4902 1249.23    4912 1248.38  4932.1 1248.85  4952.1 1248.48
  4982.2 1246.85  4990.2  1245.2  4990.5  1244.7    4994  1244.7  4994.2  1245.2
  5003.8 1245.35  5012.9  1246.4  5061.7 1247.11  5139.4 1249.63  5193.3 1252.05
  5234.3 1252.82  5503.9 1263.15  5599.1 1266.02  5687.7 1268.75  5756.6 1272.13
  5845.9  1275.6  5851.4  1276.3  5905.4 1278.75  5977.8 1282.42  6056.7 1285.29
#Mann= 5 ,-1 , 0
  3741.6     .05       0  4990.2     .05       0  4994.2     .05       0
  5599.1     .12       0  5905.4     .05       0
Bank Sta=4990.2,4994.2
XS Rating Curve= 0 ,0
Exp/Cntr=0.3,0.1

Type RM Length L Ch R = 1 ,6544    ,612,612,612
BEGIN DESCRIPTION:
Mapping XS 59bf200b
END DESCRIPTION:
XS GIS Cut Line= 2
      2769797.59      10269721.4      2769728.23     10266919.06
#Sta/Elev= 30
  2958.3 1255.14  3096.6 1255.03  3306.7 1252.35  3626.8 1251.24  3656.8 1250.24
  3786.8    1250  3796.8 1249.41  3946.9 1250.52  4096.9 1250.63    4397 1249.49
  4445.9  1248.7  4597.1 1249.73  4697.1 1249.78  4767.1 1248.92  4787.1 1249.52
  4847.2 1247.97  4877.2 1248.48  4907.2 1246.39  4927.2 1246.78  4955.2 1244.14
  4955.4 1243.64  4959.2 1244.14  4997.2  1244.2  5047.2 1247.55  5077.2 1247.75
  5227.3 1252.69  5260.2 1252.12  5338.7 1256.38  5662.3 1266.69  5761.5 1271.46
#Mann= 4 ,-1 , 0
  2958.3     .05       0  4955.2     .03       0  4959.2     .05       0
  5338.7     .12       0
Bank Sta=4955.2,4959.2
XS Rating Curve= 0 ,0
Exp/Cntr=0.3,0.1

Type RM Length L Ch R = 1 ,5932    ,932,932,932
BEGIN DESCRIPTION:
Mapping XS 3191bf29
END DESCRIPTION:
XS GIS Cut Line= 2
      2770227.64     10270095.96      2770227.64     10266976.36
#Sta/Elev= 30
  2897.3 1259.94  3060.1 1256.13  3410.1 1251.69  3610.1 1250.88  3710.1 1252.76
  3840.1 1252.92  3990.1 1252.41  4255.1 1249.86  4370.1 1247.98  4390.1 1246.81
  4460.1  1246.2  4470.1 1244.71  4549.8 1244.76  4680.1 1246.06  4860.1 1244.93
  4950.1 1243.15  4998.1 1240.12  4998.4 1239.62  5002.1 1240.12  5020.1 1241.66
  5050.1 1242.83  5210.5 1246.23  5310.7 1248.68  5362.8 1250.12    5554  1256.1
  5605.5 1257.52  5650.1 1259.85  5730.1  1261.5  5975.7 1270.23  6016.9 1271.85
#Mann= 11 ,-1 , 0
  2897.3     .05       0  4255.1     .12       0  4549.8     .05       0
  4998.1     .03       0  5002.1     .05       0  5210.5     .12       0
  5310.7     .05       0  5362.8     .12       0    5554     .05       0
  5605.5     .12       0  5975.7     .05       0
Bank Sta=4998.1,5002.1
XS Rating Curve= 0 ,0
Exp/Cntr=0.3,0.1

Type RM Length L Ch R = 1 ,5000    ,500,500,500
BEGIN DESCRIPTION:
SANFERNANDO035 10.0
END DESCRIPTION:
XS GIS Cut Line= 3
      2771155.68     10270303.07       2770907.3     10268380.55
      2771555.67     10267553.12
#Sta/Elev= 30
  3061.5 1276.33  3213.1 1269.63  3611.5 1254.43  3918.5 1248.44    3979 1249.01
  4079.8 1248.06  4120.2 1249.06  4506.8 1247.61  4614.3 1245.34  4674.8 1243.34
  4684.8 1241.97  4795.7 1240.19  4967.2  1239.6  4987.3 1237.78  4996.2  1235.7
  5008.1 1235.29  5008.5 1234.79  5013.2 1235.29  5018.8 1236.29  5039.6 1236.38
    5054 1238.21  5167.9 1240.33  5317.1 1245.78  5325.2 1245.05  5480.8 1246.87
  5650.6 1251.38    5694 1252.94  5919.8 1261.15  6008.7 1264.03  6051.2 1264.32
#Mann= 8 ,-1 , 0
  3061.5     .05       0  3213.1     .12       0  3611.5     .05       0
  5008.1     .05       0  5013.2     .05       0  5650.6     .12       0
    5694     .05       0  5919.8     .12       0
Bank Sta=5008.1,5013.2
XS Rating Curve= 0 ,0
Exp/Cntr=0.3,0.1

Type RM Length L Ch R = 1 ,4500    ,500,500,500
BEGIN DESCRIPTION:
SANFERNANDO035 9.0
END DESCRIPTION:
XS GIS Cut Line= 3
      2771305.68     10270353.14      2771341.54     10268468.29
      2771555.67     10267753.16
#Sta/Elev= 30
  3114.8 1277.81  3141.4 1276.57  3224.9 1274.04  3264.9 1273.76  3333.7 1271.29
  3541.5 1264.84  3569.9 1263.69    3805 1255.23    4055 1247.81    4295 1242.46
  4375.1 1241.49  4387.7 1241.98  4485.9 1240.38  4584.1 1240.15  4747.3 1239.08
  4825.1 1237.06  4940.4 1236.08  4952.7 1235.96  4985.2 1231.87  5002.9 1231.13
  5003.3 1230.63    5008 1231.13  5026.3 1235.29  5031.7 1237.24  5036.9  1237.9
  5064.8 1239.25  5162.9 1241.37  5256.5 1244.03  5671.8 1257.66  5746.5 1259.75
#Mann= 15 ,-1 , 0
  3114.8     .05       0  3141.4     .12       0  3333.7     .05       0
  3541.5     .12       0  3569.9     .05       0  4387.7     .12       0
  4485.9     .05       0  4584.1     .12       0  4747.3     .05       0
  4940.4     .12       0  5002.9     .07       0    5008     .12       0
  5162.9     .05       0  5256.5     .12       0  5671.8     .05       0
Bank Sta=5002.9,5008
XS Rating Curve= 0 ,0
Exp/Cntr=0.3,0.1

Type RM Length L Ch R = 1 ,4000    ,500,500,500
BEGIN DESCRIPTION:
SANFERNANDO035 8.0
END DESCRIPTION:
XS GIS Cut Line= 3
      2771605.69      10269603.1      2771691.36     10268810.51
      2771605.69     10267803.15
#Sta/Elev= 30
  4202.8 1255.36  4248.7 1252.82  4375.2 1248.43  4514.6 1244.45  4595.1  1243.1
  4625.9  1241.3  4685.6  1239.8  4838.3 1237.31  4906.9 1233.47  4947.1 1234.63
  4987.3 1233.69    4993 1230.13    5000 1230.27  5002.6 1229.01    5003 1228.51
  5007.7 1229.01  5009.3 1229.25  5027.5 1234.02  5037.5 1233.83  5057.6 1235.14
    5178 1237.43    5384 1239.13    5439  1240.5    5449 1241.89  5469.1 1241.39
  5509.2 1242.23  5539.3 1244.19  5770.2 1250.93  5992.8 1258.76    6011 1258.96
#Mann= 8 ,-1 , 0
  4202.8     .12       0  4375.2     .05       0  4838.3     .12       0
  5002.6     .07       0  5007.7     .12       0  5009.3     .05       0
    5384     .12       0  5992.8     .05       0
Bank Sta=5002.6,5007.7
XS Rating Curve= 0 ,0
Exp/Cntr=0.3,0.1

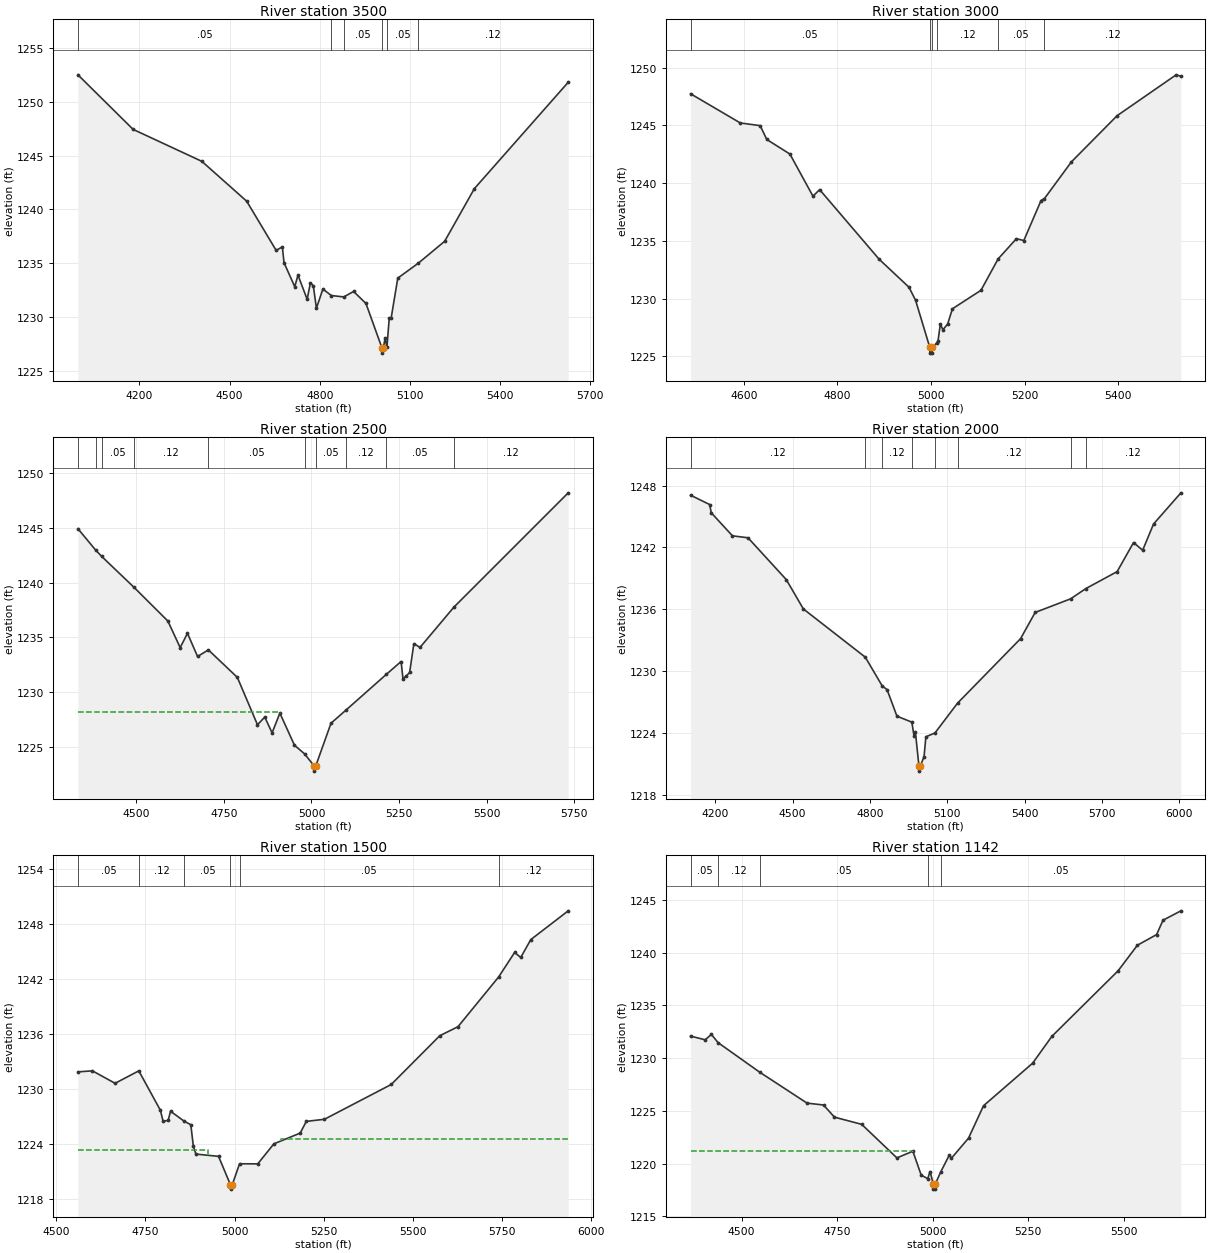
Type RM Length L Ch R = 1 ,3500    ,500,500,500
BEGIN DESCRIPTION:
SANFERNANDO035 7.0
END DESCRIPTION:
XS GIS Cut Line= 3
      2771755.69      10269603.1       2771997.3      10268628.3
      2772405.71     10268153.08
#Sta/Elev= 30
  3995.7 1252.52  4179.4 1247.44  4407.8 1244.47    4557 1240.76  4655.1 1236.18
  4675.7 1236.51  4681.2 1235.04  4716.9  1232.8  4727.7 1233.88  4758.1 1231.63
  4769.1 1233.17  4778.7 1232.88    4789  1230.8  4810.5 1232.58  4838.7 1231.98
    4880 1231.85  4912.6 1232.36  4953.8 1231.24  5006.7 1227.12  5007.1 1226.62
    5012 1227.12    5017 1227.99  5023.6 1227.21  5031.2 1229.86  5037.8 1229.92
  5059.6  1233.6  5127.9 1234.99  5215.6 1237.03  5314.4 1241.93  5626.6 1251.83
#Mann= 6 ,-1 , 0
  3995.7     .05       0  4838.7     .12       0    4880     .05       0
  5006.7     .05       0  5023.6     .05       0  5127.9     .12       0
Bank Sta=5006.7,5012
XS Rating Curve= 0 ,0
Exp/Cntr=0.3,0.1

Type RM Length L Ch R = 1 ,3000    ,500,500,500
BEGIN DESCRIPTION:
SANFERNANDO035 6.0
END DESCRIPTION:
XS GIS Cut Line= 3
      2772005.67     10269303.12      2772357.07       10268928.
      2772455.69     10268403.09
#Sta/Elev= 30
    4486 1247.74  4592.3 1245.21  4634.7 1244.98  4648.9 1243.78  4698.3 1242.52
  4747.6 1238.87  4761.8 1239.44  4889.3  1233.4  4952.8 1230.99  4966.9 1229.86
  4997.3 1225.78  4997.7 1225.28  5002.2 1225.28  5002.6 1225.78    5012 1226.15
  5014.8  1226.3  5019.9 1227.81  5025.3  1227.3  5035.5  1227.8  5045.7 1229.12
  5106.7 1230.72  5143.4 1233.44  5182.5 1235.19  5198.3 1235.03  5235.1 1238.49
  5242.5 1238.67    5300 1241.84  5397.7 1245.84  5523.9 1249.38  5534.1 1249.25
#Mann= 6 ,-1 , 0
    4486     .05       0  4997.3     .05       0  5002.6     .05       0
    5012     .12       0  5143.4     .05       0  5242.5     .12       0
Bank Sta=4997.3,5002.6
XS Rating Curve= 0 ,0
Exp/Cntr=0.3,0.1

Type RM Length L Ch R = 1 ,2500    ,500,500,500
BEGIN DESCRIPTION:
SANFERNANDO035 5.0
END DESCRIPTION:
XS GIS Cut Line= 3
      2772255.66     10269553.13       2772775.2       10269135.
      2772505.69     10268453.13
#Sta/Elev= 30
  4333.1 1244.92  4383.3 1242.98  4401.2 1242.38  4493.3 1239.56  4589.9 1236.48
  4625.1 1234.05  4645.9 1235.36  4674.7 1233.24  4705.6 1233.84  4788.3 1231.33
  4845.8    1227  4866.6  1227.7  4887.5 1226.26  4909.8 1228.06  4951.4 1225.13
  4980.2 1224.34  5007.1 1223.26  5007.5 1222.76  5012.5 1223.26  5055.8 1227.14
  5098.9 1228.35  5213.9 1231.61  5255.9 1232.78  5261.3 1231.21  5270.8 1231.46
  5280.3 1231.78  5292.4 1234.41    5310 1234.07  5406.7 1237.75  5733.2  1248.2
#Mann= 10 ,-1 , 0
  4333.1     .05       0  4383.3     .12       0  4401.2     .05       0
  4493.3     .12       0  4705.6     .05       0  4980.2     .07       0
  5012.5     .05       0  5098.9     .12       0  5213.9     .05       0
  5406.7     .12       0
#XS Ineff= 2 , 0
         4909.09 1228.21
Permanent Ineff=
       F       F
Bank Sta=5007.1,5012.5
XS Rating Curve= 0 ,0
Exp/Cntr=0.3,0.1

Type RM Length L Ch R = 1 ,2000    ,500,500,500
BEGIN DESCRIPTION:
SANFERNANDO035 4.0
END DESCRIPTION:
XS GIS Cut Line= 3
      2772855.68     10269953.12      2773272.97       10269160.
      2772555.66     10268453.09
#Sta/Elev= 30
  4103.8 1247.07  4178.1 1246.16  4183.8 1245.37  4266.3 1243.13  4326.7 1242.94
  4475.4 1238.88  4541.5 1236.04    4782 1231.36    4848 1228.56  4866.4 1228.22
  4904.8 1225.64  4962.7 1225.06  4970.9 1223.75  4976.6 1224.06  4990.2 1220.81
  4990.7 1220.31  4995.7 1220.81  5010.1 1221.72  5017.1 1223.64  5052.4 1224.01
    5140  1226.9  5384.8 1233.16  5441.4  1235.7  5579.1 1237.02  5637.8 1238.01
  5759.6 1239.66  5823.3 1242.48  5858.6 1241.73    5901 1244.28  6007.1  1247.3
#Mann= 8 ,-1 , 0
  4103.8     .12       0    4782     .05       0    4848     .12       0
  4962.7     .05       0  5052.4     .05       0    5140     .12       0
  5579.1     .05       0  5637.8     .12       0
Bank Sta=4990.2,4995.7
XS Rating Curve= 0 ,0
Exp/Cntr=0.3,0.1

Type RM Length L Ch R = 1 ,1500    ,358,358,358
BEGIN DESCRIPTION:
SANFERNANDO035 3.0
END DESCRIPTION:
XS GIS Cut Line= 3
      2773725.93     10269049.76      2773399.68     10268755.73
      2772555.69     10268353.11
#Sta/Elev= 30
  4560.8 1231.84  4601.4 1231.95    4665 1230.59  4731.4 1231.95    4792 1227.64
  4799.5 1226.44  4813.7 1226.54  4820.4 1227.54  4859.3 1226.43  4877.2 1226.07
  4884.2 1223.75  4891.4 1222.86  4954.9 1222.61  4988.1 1219.53  4988.5 1219.03
  4993.6 1219.53  5013.8  1221.8  5064.8 1221.79  5110.1 1223.98  5183.8 1225.15
  5200.9 1226.43  5251.8 1226.66  5438.9 1230.46  5575.1 1235.79    5626 1236.77
  5739.9  1242.2  5784.8 1244.88    5802 1244.34  5830.2 1246.29  5935.1 1249.43
#Mann= 6 ,-1 , 0
  4560.8     .05       0  4731.4     .12       0  4859.3     .05       0
  4988.1     .07       0  5013.8     .05       0  5739.9     .12       0
#XS Ineff= 2 , 0
         4925.45 1223.33 5130.91         1224.54
Permanent Ineff=
       F       F
Bank Sta=4988.1,4993.6
XS Rating Curve= 0 ,0
Exp/Cntr=0.3,0.1

Type RM Length L Ch R = 1 ,1142    ,492,492,492
BEGIN DESCRIPTION:
Mapping XS 13716c77
END DESCRIPTION:
XS GIS Cut Line= 4
       2773705.7     10268953.14       2773582.4     10268664.95
      2773381.02     10268433.37      2772788.78     10268137.25
#Sta/Elev= 30
  4366.5 1232.09  4404.6 1231.74  4420.9 1232.25  4438.4 1231.47  4547.3 1228.67
  4671.1 1225.74  4714.3 1225.56  4742.8 1224.41    4814 1223.73  4906.1 1220.55
  4947.9 1221.18  4969.7 1218.92  4986.8 1218.58  4992.8 1219.26  5001.3 1218.09
  5001.8 1217.59  5006.4 1217.59  5006.8 1218.09  5020.9 1219.23  5043.2 1220.81
  5048.8 1220.52  5093.5 1222.42  5132.7 1225.49  5261.1 1229.52  5311.6 1232.07
  5484.8 1238.28  5535.2  1240.7  5585.5 1241.71  5602.2 1243.07    5649 1243.96
#Mann= 5 ,-1 , 0
  4366.5     .05       0  4438.4     .12       0  4547.3     .05       0
  4986.8     .07       0  5020.9     .05       0
#XS Ineff= 2 , 0
         4948.18 1221.25
Permanent Ineff=
       F       F
Bank Sta=5001.3,5006.8
XS Rating Curve= 0 ,0
Exp/Cntr=0.3,0.1

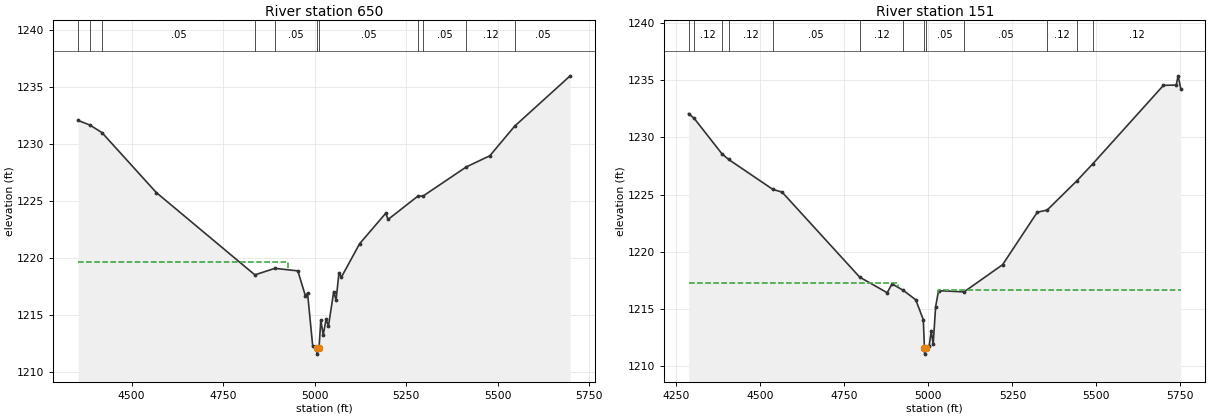
Type RM Length L Ch R = 1 ,650     ,499,499,499
BEGIN DESCRIPTION:
SANFERNANDO035 2.0
END DESCRIPTION:
XS GIS Cut Line= 3
      2773705.69     10268953.07        2773824.       10268318.
      2773381.05     10267778.94
#Sta/Elev= 30
    4354 1232.09  4386.1 1231.69  4419.4 1231.02  4567.6 1225.77  4836.8 1218.55
  4891.4 1219.12  4954.1  1218.9  4974.5 1216.74  4980.7 1216.93  4994.8 1212.28
  5006.2  1212.1  5006.6  1211.6  5011.9  1212.1  5016.9 1214.59  5023.4 1213.27
  5031.2 1214.65  5037.7 1214.05  5052.1 1217.08  5058.5 1216.33  5066.4 1218.73
  5072.9 1218.34  5122.8 1221.28  5194.1 1223.95  5200.6 1223.41  5282.6 1225.47
  5296.1 1225.46  5414.4 1228.02  5478.3 1228.99  5546.2 1231.59  5697.7    1236
#Mann= 11 ,-1 , 0
    4354     .05       0  4386.1     .12       0  4419.4     .05       0
  4836.8     .12       0  4891.4     .05       0  5006.2     .07       0
  5011.9     .05       0  5282.6     .12       0  5296.1     .05       0
  5414.4     .12       0  5546.2     .05       0
#XS Ineff= 2 , 0
         4927.27 1219.68
Permanent Ineff=
       F       F
Bank Sta=5006.2,5011.9
XS Rating Curve= 0 ,0
Exp/Cntr=0.3,0.1

Type RM Length L Ch R = 1 ,151     ,0,0,0
BEGIN DESCRIPTION:
SANFERNANDO035 1.0
END DESCRIPTION:
XS GIS Cut Line= 3
      2773705.69     10268953.11      2774266.75       10268512.
       2773905.7     10267853.14
#Sta/Elev= 30
  4286.3 1232.09  4303.1 1231.66  4385.8 1228.56  4405.3 1228.08  4536.5 1225.47
  4564.6 1225.22  4795.5 1217.79  4877.3 1216.43  4891.8  1217.2  4925.6 1216.63
  4962.3 1215.81  4984.8 1214.07  4988.3 1211.56  4988.8 1211.06    4994 1211.56
  5002.2 1211.76  5008.5 1213.09  5014.2 1211.91  5021.5 1215.22  5030.3 1216.61
    5106  1216.5  5220.9 1218.88  5324.2 1223.47  5353.3 1223.65  5442.2 1226.22
  5489.7 1227.71  5699.7 1234.56  5737.6 1234.58  5743.3 1235.39  5751.3 1234.25
#Mann= 13 ,-1 , 0
  4286.3     .05       0  4303.1     .12       0  4385.8     .05       0
  4405.3     .12       0  4536.5     .05       0  4795.5     .12       0
  4925.6     .05       0  4988.3     .07       0    4994     .05       0
    5106     .05       0  5353.3     .12       0  5442.2     .05       0
  5489.7     .12       0
#XS Ineff= 2 , 0
            4910 1217.32 5029.09         1216.68
Permanent Ineff=
       F       F
Bank Sta=4988.3,4994
XS Rating Curve= 0 ,0
Exp/Cntr=0.3,0.1

Chan Stop Cuts=-1
Use User Specified Reach Order=0
Composite Channel Slope=5