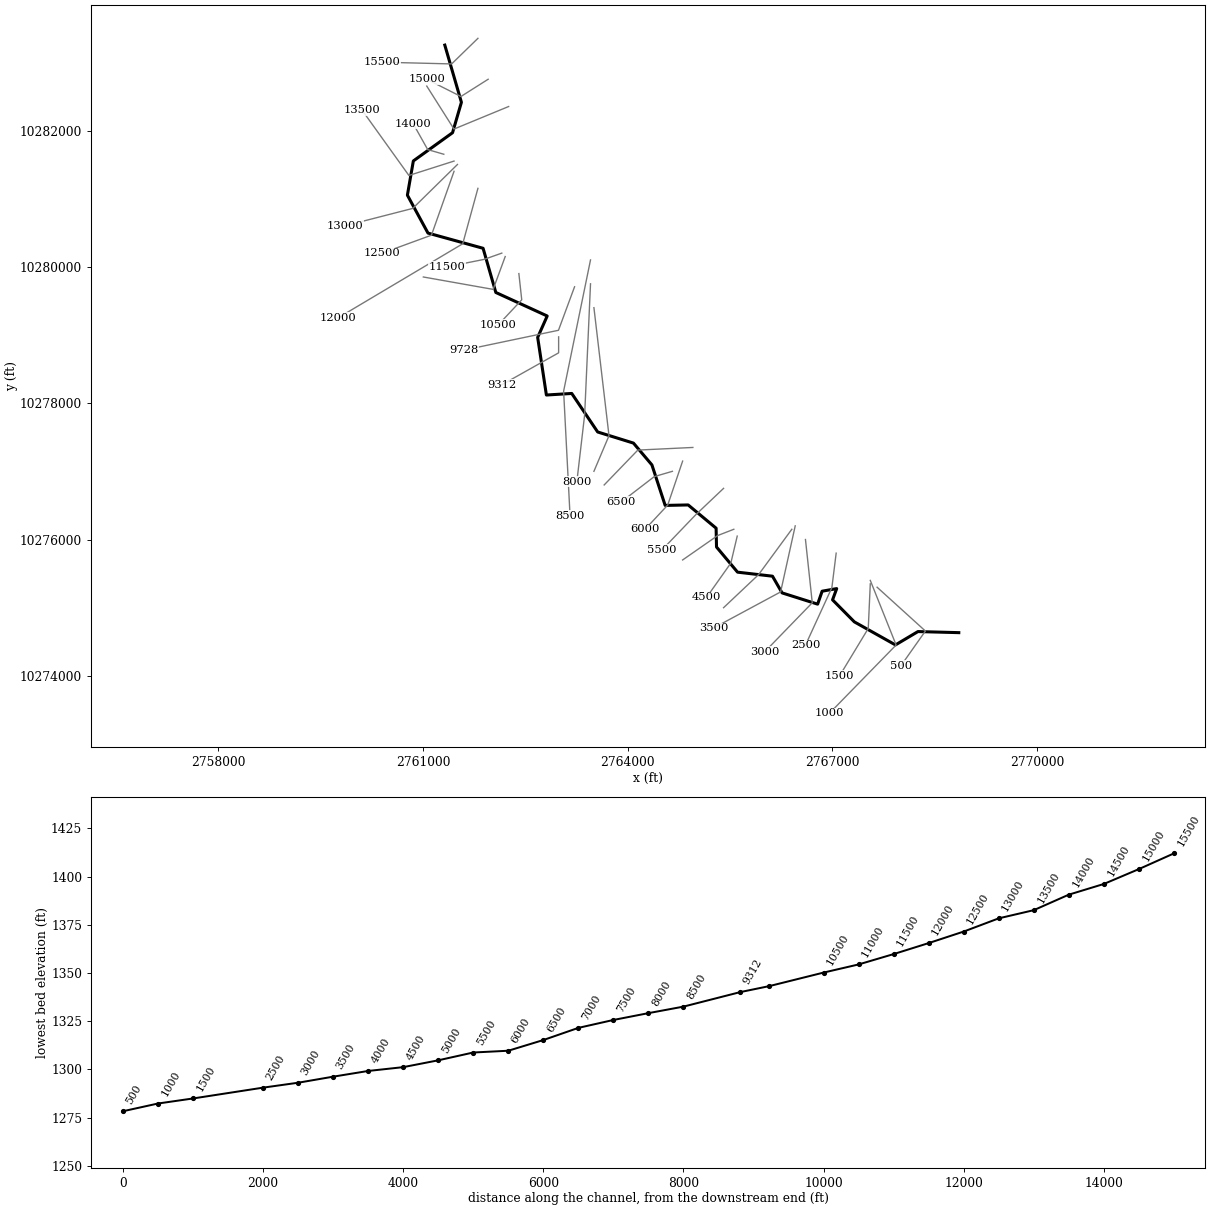
--- SANFERNANDO037.prj (project) ---

Proj Title=SANFERNANDO037 Base Level Engineering
Current Plan=p01
Default Exp/Contr=0.3,0.1
English Units
Geom File=g01
Flow File=f01
Plan File=p01
Y Axis Title=Elevation
X Axis Title(PF)=Main Channel Distance
X Axis Title(XS)=Station
BEGIN DESCRIPTION:
SANFERNANDO037
END DESCRIPTION:
DSS Export Rating Curves= 0
DSS Export Rating Curve Sorted= 0
DSS Export Volume Flow Curves= 0
DXF OffsetX= 0
DXF OffsetY= 0
DXF ScaleX= 1
DXF ScaleY= 10

--- SANFERNANDO037.p01 (plan) ---

Plan Title=Multiple Run
Short Identifier=Multiple
Geom File=g01
Flow File=f01
Subcritical Flow
K Sum by GR= 0
Std Step Tol= 0.01
Critical Tol= 0.01
Num of Std Step Trials= 20
Max Error Tol= 0.3
Flow Tol Ratio= 0.001
Split Flow NTrial= 30
Split Flow Tol= 0.02
Split Flow Ratio= 0.02
Log Output Level= 0
Friction Slope Method= 1
Unsteady Friction Slope Method= 2
Unsteady Bridges Friction Slope Method= 1
Parabolic Critical Depth
Global Vel Dist=  1 , 1 , 1
Global Log Level= 0
CheckData=True
Encroach Param= -1, 0, 0, 0
BEGIN DESCRIPTION:
Multiple Run
END DESCRIPTION:

--- SANFERNANDO037.f01 (steady flow) ---

Flow Title=Multiple
Number of Profiles=7
Profile Names=10-year,25-year,50-year,1pct_min,100-year,1pct_plu,500-year
River Rch & RM= SANFERNANDO037,Reach-1,15500
     458     745    1630    1365    2316    3928    3407
River Rch & RM= SANFERNANDO037,Reach-1,5500
     707    1191    1398    1037    1870    3374    2541
Boundary for River Rch & Prof#=SANFERNANDO037,Reach-1,1
Up Type=0
Dn Type=3
Dn Slope=0.005
Boundary for River Rch & Prof#=SANFERNANDO037,Reach-1,2
Up Type=0
Dn Type=3
Dn Slope=0.005
Boundary for River Rch & Prof#=SANFERNANDO037,Reach-1,3
Up Type=0
Dn Type=3
Dn Slope=0.005
Boundary for River Rch & Prof#=SANFERNANDO037,Reach-1,4
Up Type=0
Dn Type=3
Dn Slope=0.005
Boundary for River Rch & Prof#=SANFERNANDO037,Reach-1,5
Up Type=0
Dn Type=3
Dn Slope=0.005
Boundary for River Rch & Prof#=SANFERNANDO037,Reach-1,6
Up Type=0
Dn Type=3
Dn Slope=0.005
Boundary for River Rch & Prof#=SANFERNANDO037,Reach-1,7
Up Type=0
Dn Type=3
Dn Slope=0.005

--- SANFERNANDO037.g01 (geometry) ---

Geom Title=Existing Conditions
Program Version=4.10

River Reach=SANFERNANDO037  ,Reach-1
Reach XY= 30
      2761320.25       10283254.      2761563.75       10282415.
      2761433.75       10281969.      2760859.25       10281555.
        2760772.       10281053.      2761073.75       10280497.
      2761881.25       10280274.        2762068.       10279626.
        2762821.       10279281.      2762681.25       10278967.
        2762809.       10278122.      2763180.75       10278145.
       2763560.5       10277580.        2764085.       10277417.
       2764355.5       10277097.      2764549.75       10276503.
      2764886.75       10276510.      2765296.25       10276169.
      2765302.25       10275893.       2765610.5       10275524.
       2766122.5       10275465.      2766263.25       10275220.
        2766784.       10275055.        2766850.       10275245.
       2767063.5       10275283.      2767002.75       10275118.
      2767322.25       10274795.       2767924.5       10274457.
       2768254.5       10274653.      2768852.75       10274637.

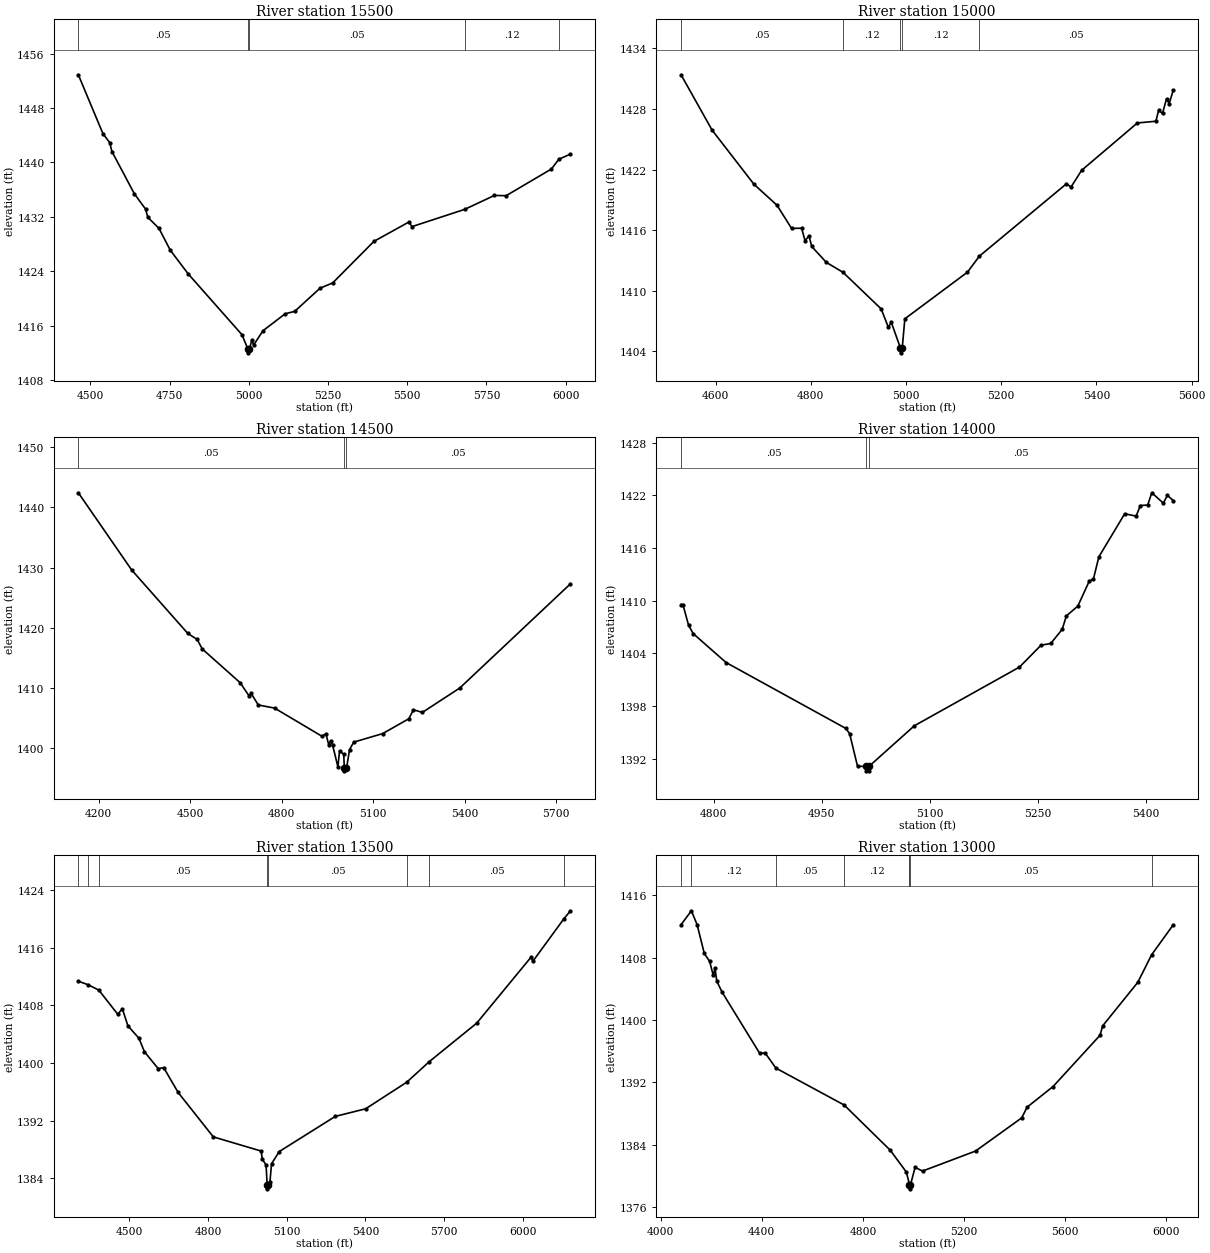
Type RM Length L Ch R = 1 ,15500   ,500,500,500
BEGIN DESCRIPTION:
SANFERNANDO037 31.0
END DESCRIPTION:
XS GIS Cut Line= 3
      2761805.69     10283353.12       2761420.6     10282977.85
      2760405.72     10283003.11
#Sta/Elev= 30
  4462.3  1452.9  4540.1 1444.22  4561.2 1442.93  4568.4  1441.6  4639.1 1435.39
  4674.4 1433.14  4681.6 1431.93  4716.8  1430.3  4752.3  1427.1  4808.9 1423.61
  4978.6 1414.66  4997.8 1412.49    4998 1411.99  5001.8 1412.49  5010.2 1413.92
  5015.2 1413.12  5044.9 1415.24    5115 1417.74    5145 1418.09    5225  1421.5
    5265 1422.28    5395 1428.39  5505.1 1431.23  5515.1 1430.56  5681.6  1433.1
  5775.2 1435.15  5812.2 1435.11  5955.2 1439.04  5978.4 1440.47  6015.2 1441.23
#Mann= 5 ,-1 , 0
  4462.3     .05       0  4997.8     .05       0  5001.8     .05       0
  5681.6     .12       0  5978.4     .05       0
Bank Sta=4997.8,5001.8
XS Rating Curve= 0 ,0
Exp/Cntr=0.3,0.1

Type RM Length L Ch R = 1 ,15000   ,500,500,500
BEGIN DESCRIPTION:
SANFERNANDO037 30.0
END DESCRIPTION:
XS GIS Cut Line= 3
      2761955.65     10282753.09      2761556.65     10282500.19
      2761055.67     10282753.12
#Sta/Elev= 30
  4527.6 1431.38  4592.8  1425.9  4680.9 1420.53  4729.2 1418.46  4759.7 1416.17
  4780.9 1416.19    4788 1414.94  4796.2 1415.44  4802.1 1414.38  4832.6 1412.81
  4867.8 1411.82  4947.9  1408.2  4963.1 1406.36    4969 1406.89  4988.2 1404.35
  4988.5 1403.85  4992.2 1404.35  4997.6 1407.22  5129.2 1411.84  5154.1 1413.42
  5337.1 1420.59  5346.6 1420.26  5368.9 1421.92    5486 1426.61  5524.9 1426.78
  5530.5 1427.85  5538.8 1427.56  5547.2    1429  5552.8 1428.52  5561.2 1429.83
#Mann= 5 ,-1 , 0
  4527.6     .05       0  4867.8     .12       0  4988.2     .07       0
  4992.2     .12       0  5154.1     .05       0
Bank Sta=4988.2,4992.2
XS Rating Curve= 0 ,0
Exp/Cntr=0.3,0.1

Type RM Length L Ch R = 1 ,14500   ,500,500,500
BEGIN DESCRIPTION:
SANFERNANDO037 29.0
END DESCRIPTION:
XS GIS Cut Line= 3
       2762255.7     10282353.12      2761454.83     10282022.58
      2761055.66     10282653.15
#Sta/Elev= 30
  4133.6 1442.45  4308.1 1429.61  4491.8 1419.05  4523.1 1418.02  4539.6 1416.44
  4663.7 1410.83    4694 1408.55  4699.4 1409.07  4723.3 1407.11  4776.6 1406.59
  4930.9 1401.93    4945 1402.27  4954.8 1400.37  4960.3 1401.16  4966.6 1400.47
  4984.2 1396.81  4989.6 1399.46  5003.3 1398.89  5005.2 1396.64  5005.4 1396.14
  5009.2 1396.64  5013.1 1396.78  5022.4 1399.69  5036.1 1400.92  5130.8 1402.34
  5216.5 1404.81  5231.8 1406.31    5261 1405.87  5383.5 1409.93  5746.3 1427.29
#Mann= 3 ,-1 , 0
  4133.6     .05       0  5005.2     .05       0  5009.2     .05       0
Bank Sta=5005.2,5009.2
XS Rating Curve= 0 ,0
Exp/Cntr=0.3,0.1

Type RM Length L Ch R = 1 ,14000   ,500,500,500
BEGIN DESCRIPTION:
SANFERNANDO037 28.0
END DESCRIPTION:
XS GIS Cut Line= 3
       2761305.7     10281653.11      2761069.98     10281721.37
      2760855.67     10282103.13
#Sta/Elev= 30
  4754.6 1409.54  4757.2 1409.54    4765  1407.2  4771.4 1406.24  4817.1 1402.94
  4983.4 1395.43  4988.6 1394.84  4999.6 1391.12  5011.4  1391.1  5011.6  1390.6
  5015.1  1390.6  5015.4  1391.1  5078.4 1395.73  5224.4 1402.42  5254.3 1404.91
  5267.8 1405.11  5283.8 1406.73  5289.5 1408.25  5305.4 1409.37  5321.4 1412.23
  5327.1 1412.46  5334.6 1414.98  5370.5 1419.89  5386.4 1419.62  5392.2 1420.83
  5402.4 1420.88  5408.1 1422.28  5424.1  1421.1  5429.8 1421.98  5437.8  1421.4
#Mann= 3 ,-1 , 0
  4754.6     .05       0  5011.4     .05       0  5015.4     .05       0
Bank Sta=5011.4,5015.4
XS Rating Curve= 0 ,0
Exp/Cntr=0.3,0.1

Type RM Length L Ch R = 1 ,13500   ,500,500,500
BEGIN DESCRIPTION:
SANFERNANDO037 27.0
END DESCRIPTION:
XS GIS Cut Line= 3
      2761455.72     10281553.12       2760794.2     10281341.99
      2760105.68     10282303.12
#Sta/Elev= 30
  4305.6 1411.33  4344.3 1410.82  4383.9 1410.09  4455.7 1406.76  4473.6  1407.5
  4494.6 1405.15  4536.6 1403.43  4557.6 1401.56  4610.1 1399.22    4631 1399.36
  4686.3 1395.91  4820.3 1389.76    5003 1387.79  5006.8  1386.7  5021.5 1385.86
  5025.7 1383.06  5025.9 1382.56  5029.7 1383.06  5036.3 1383.53  5042.4 1386.04
  5071.9 1387.73  5285.6  1392.6  5401.1 1393.65  5557.8 1397.33  5643.7 1400.18
  5824.8 1405.52  6032.4 1414.68  6038.6 1414.08  6156.8 1419.96  6182.3 1421.09
#Mann= 8 ,-1 , 0
  4305.6     .05       0  4344.3     .12       0  4383.9     .05       0
  5025.7     .05       0  5029.7     .05       0  5557.8     .12       0
  5643.7     .05       0  6156.8     .12       0
Bank Sta=5025.7,5029.7
XS Rating Curve= 0 ,0
Exp/Cntr=0.3,0.1

Type RM Length L Ch R = 1 ,13000   ,500,500,500
BEGIN DESCRIPTION:
SANFERNANDO037 26.0
END DESCRIPTION:
XS GIS Cut Line= 3
      2761505.65     10281503.08      2760850.27     10280858.84
      2759855.72     10280603.12
#Sta/Elev= 30
    4081 1412.21  4121.8    1414  4144.6 1412.21  4172.9 1408.52    4194 1407.51
  4208.2 1405.73  4215.3 1406.63  4222.3 1404.97  4243.6 1403.54  4392.1  1395.7
  4413.3 1395.76  4456.1 1393.81  4725.7 1389.08  4908.3 1383.27  4971.9 1380.47
  4983.5 1378.96  4984.1 1378.82  4984.3 1378.32  4988.1 1378.82  5006.4 1381.08
  5035.7  1380.6  5245.6 1383.17  5428.1 1387.43  5449.3  1388.8    5552 1391.45
  5737.8 1398.03  5748.2 1399.24    5887 1404.82  5941.3 1408.34  6026.9 1412.19
#Mann= 8 ,-1 , 0
    4081     .05       0  4121.8     .12       0  4456.1     .05       0
  4725.7     .12       0  4983.5     .05       0  4984.1     .05       0
  4988.1     .05       0  5941.3     .12       0
Bank Sta=4984.1,4988.1
XS Rating Curve= 0 ,0
Exp/Cntr=0.3,0.1

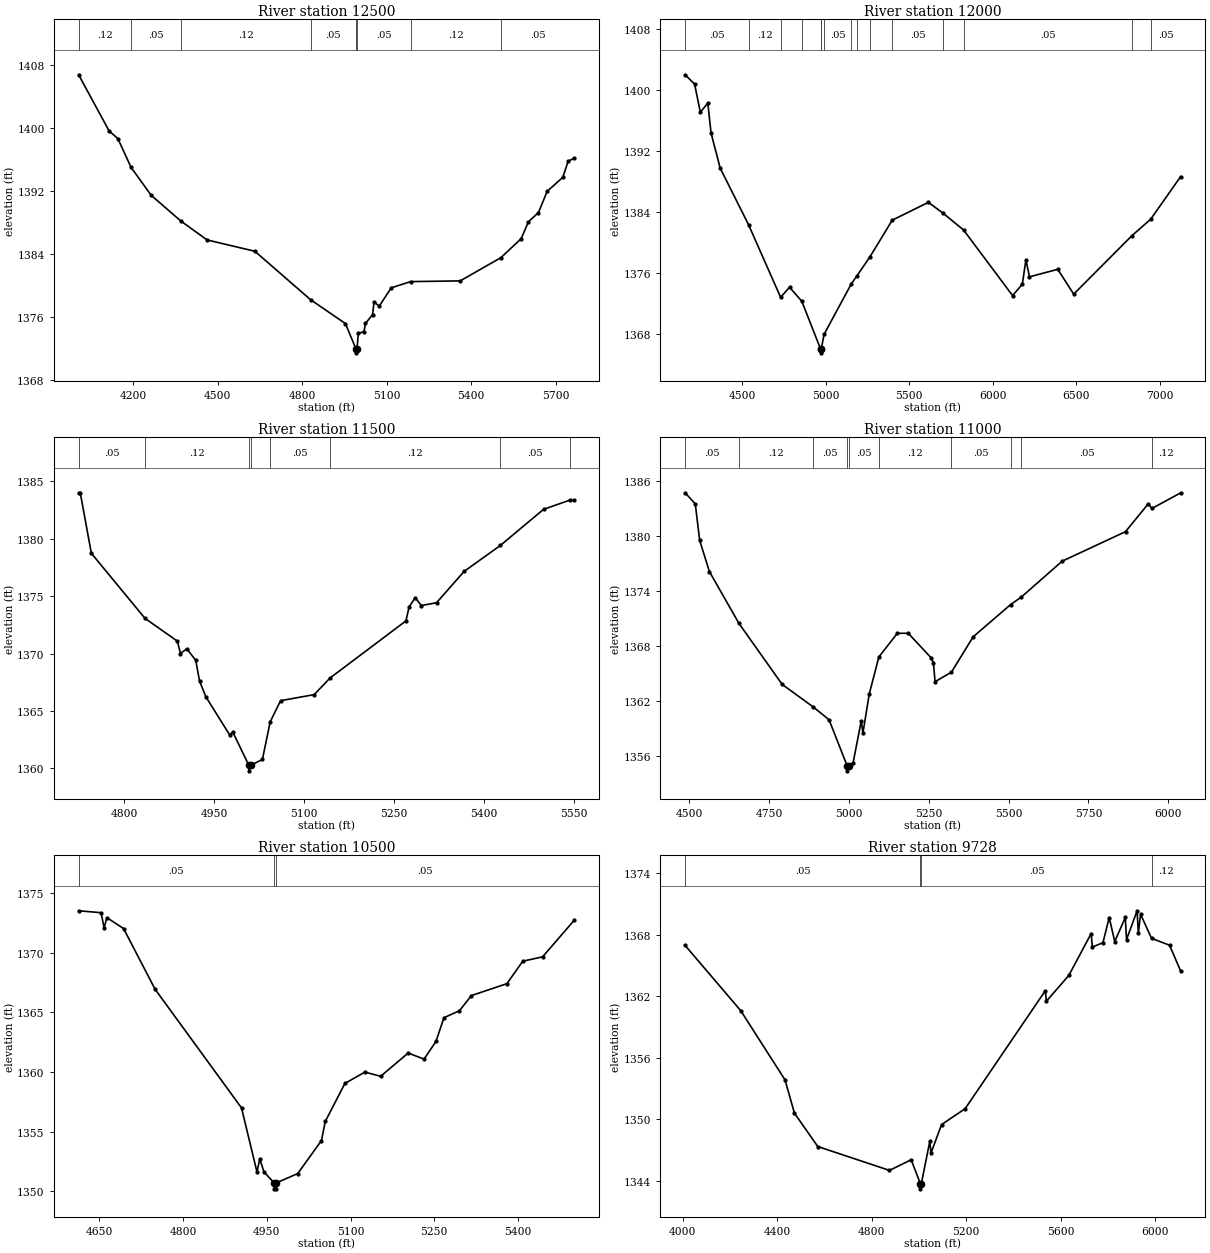
Type RM Length L Ch R = 1 ,12500   ,500,500,500
BEGIN DESCRIPTION:
SANFERNANDO037 25.0
END DESCRIPTION:
XS GIS Cut Line= 3
      2761455.67     10281403.08      2761124.56     10280466.28
      2760405.71     10280203.12
#Sta/Elev= 30
  4006.4 1406.76  4114.6 1399.63  4145.5 1398.67  4192.7    1395  4263.8 1391.47
  4369.5 1388.19  4462.4  1385.8  4632.1 1384.36  4829.6 1378.22  4953.6 1375.18
  4990.8 1371.97    4991 1371.47  4994.8 1371.97    4999 1373.93  5019.3 1374.17
  5024.6  1375.2  5049.8 1376.31  5055.1 1377.94  5073.3 1377.39  5116.1 1379.72
    5185 1380.51  5360.9  1380.6  5505.8 1383.56  5577.8 1385.98    5603  1388.1
  5638.8 1389.28  5669.7 1391.97  5725.1 1393.74  5744.2 1395.79  5765.5 1396.17
#Mann= 8 ,-1 , 0
  4006.4     .12       0  4192.7     .05       0  4369.5     .12       0
  4829.6     .05       0  4990.8     .05       0  4994.8     .05       0
    5185     .12       0  5505.8     .05       0
Bank Sta=4990.8,4994.8
XS Rating Curve= 0 ,0
Exp/Cntr=0.3,0.1

Type RM Length L Ch R = 1 ,12000   ,500,500,500
BEGIN DESCRIPTION:
SANFERNANDO037 24.0
END DESCRIPTION:
XS GIS Cut Line= 3
      2761805.68      10281153.1      2761582.94     10280340.38
      2759755.65     10279253.09
#Sta/Elev= 30
  4157.3 1401.97  4214.2 1400.75  4248.7 1397.06  4293.5 1398.26  4312.8 1394.33
  4367.6 1389.72  4538.1 1382.27  4729.7 1372.77  4783.1  1374.1  4856.7 1372.25
    4969 1365.99  4969.2 1365.49    4973 1365.99  4990.3 1367.93  5153.7 1374.56
  5187.6 1375.61  5265.8 1378.12  5398.6  1382.9    5615 1385.23  5704.4 1383.79
    5826  1381.6  6119.4    1373  6177.8  1374.5  6199.3 1377.68  6220.7 1375.46
  6390.1 1376.45  6485.6 1373.19  6834.4 1380.86  6946.4 1383.01  7126.3 1388.61
#Mann= 15 ,-1 , 0
  4157.3     .05       0  4538.1     .12       0  4729.7     .05       0
  4856.7     .12       0    4969     .05       0    4973     .12       0
  4990.3     .05       0  5153.7     .12       0  5187.6     .05       0
  5265.8     .12       0  5398.6     .05       0  5704.4     .12       0
    5826     .05       0  6834.4     .12       0  6946.4     .05       0
Bank Sta=4969,4973
XS Rating Curve= 0 ,0
Exp/Cntr=0.3,0.1

Type RM Length L Ch R = 1 ,11500   ,500,500,500
BEGIN DESCRIPTION:
SANFERNANDO037 23.0
END DESCRIPTION:
XS GIS Cut Line= 3
       2762155.7     10280203.12      2761895.85     10280111.01
      2761355.72     10280003.12
#Sta/Elev= 30
  4724.3 1384.01    4727 1384.01  4745.5 1378.74    4835 1373.07  4888.9 1371.09
  4894.2 1370.01  4904.7 1370.42  4919.7 1369.41  4925.9 1367.62  4936.5 1366.24
  4976.2 1362.92  4981.5 1363.16    5008 1360.29  5008.3 1359.79    5012 1360.29
  5030.8 1360.78  5043.8 1364.06  5061.1  1365.9  5117.2 1366.43  5143.7 1367.88
  5270.2 1372.85  5275.5 1374.07  5285.7 1374.87  5295.9 1374.19  5321.2 1374.43
  5367.2 1377.16  5427.9 1379.43  5499.8 1382.57  5543.1 1383.36  5550.8 1383.37
#Mann= 8 ,-1 , 0
  4724.3     .05       0    4835     .12       0    5008     .07       0
    5012     .12       0  5043.8     .05       0  5143.7     .12       0
  5427.9     .05       0  5543.1     .12       0
Bank Sta=5008,5012
XS Rating Curve= 0 ,0
Exp/Cntr=0.3,0.1

Type RM Length L Ch R = 1 ,11000   ,500,500,500
BEGIN DESCRIPTION:
SANFERNANDO037 22.0
END DESCRIPTION:
XS GIS Cut Line= 3
      2762205.68     10280153.09      2762028.45     10279671.35
      2761005.68     10279853.11
#Sta/Elev= 30
  4486.7 1384.74  4518.6 1383.53  4532.4 1379.54  4562.8 1376.15  4655.5 1370.49
  4790.6 1363.85  4887.9 1361.39  4937.6 1359.99  4994.8 1354.92    4995 1354.42
  4998.8 1354.92    5013 1355.31  5038.5 1359.88  5043.6 1358.53  5063.8 1362.84
  5093.6 1366.84  5151.5 1369.42  5185.6 1369.42  5256.7 1366.77  5264.5 1366.22
  5269.6 1364.14    5321 1365.18  5388.8 1369.03  5506.2 1372.55  5539.2 1373.35
  5667.7 1377.28  5866.1  1380.5  5937.2 1383.53  5948.8 1383.03  6038.8 1384.73
#Mann= 10 ,-1 , 0
  4486.7     .05       0  4655.5     .12       0  4887.9     .05       0
  4994.8     .05       0  4998.8     .05       0  5093.6     .12       0
    5321     .05       0  5506.2     .12       0  5539.2     .05       0
  5948.8     .12       0
Bank Sta=4994.8,4998.8
XS Rating Curve= 0 ,0
Exp/Cntr=0.3,0.1

Type RM Length L Ch R = 1 ,10500   ,772,772,772
BEGIN DESCRIPTION:
SANFERNANDO037 21.0
END DESCRIPTION:
XS GIS Cut Line= 3
      2762405.68     10279903.11      2762447.77      10279518.4
      2762105.66     10279153.08
#Sta/Elev= 30
    4613 1373.52  4653.2 1373.36  4658.6 1372.09  4663.7 1372.94  4693.5 1372.03
  4749.9 1366.94  4904.7 1356.99  4932.4 1351.62  4937.4  1352.7    4945 1351.62
  4963.1  1350.7  4963.3  1350.2  4966.8  1350.2  4967.1  1350.7  5005.4 1351.48
  5047.9 1354.25  5054.7 1355.85  5089.9 1359.04  5125.6 1359.99  5153.9 1359.64
  5203.2 1361.59  5231.6 1361.08    5253 1362.56  5267.2 1364.55  5295.1 1365.14
  5316.5 1366.41  5380.1 1367.41  5408.4 1369.29    5444 1369.66  5500.5 1372.72
#Mann= 3 ,-1 , 0
    4613     .05       0  4963.1     .05       0  4967.1     .05       0
Bank Sta=4963.1,4967.1
XS Rating Curve= 0 ,0
Exp/Cntr=0.3,0.1

Type RM Length L Ch R = 1 ,9728    ,416,416,416
BEGIN DESCRIPTION:
Mapping XS 3efb21ab
END DESCRIPTION:
XS GIS Cut Line= 3
      2763221.97     10279709.66      2762986.14     10279071.51
      2761599.81     10278780.38
#Sta/Elev= 30
  4010.4 1366.96  4245.7  1360.6  4433.2 1353.84  4473.1 1350.59  4571.8 1347.34
  4875.1 1345.01  4967.1 1346.05    5006 1343.71  5006.2 1343.21    5010 1343.71
  5045.8 1347.84  5050.9  1346.7  5095.7 1349.48  5195.4 1351.03  5534.3 1362.53
  5539.4 1361.52  5634.1 1364.03  5728.7 1368.12  5733.8  1366.8  5778.6 1367.23
    5805 1369.68  5828.5 1367.34  5873.2 1369.69  5878.3 1367.53  5923.1 1370.34
  5928.2 1368.15  5937.8    1370  5984.1 1367.65  6060.4 1366.98  6107.3 1364.46
#Mann= 4 ,-1 , 0
  4010.4     .05       0    5006     .03       0    5010     .05       0
  5984.1     .12       0
Bank Sta=5006,5010
XS Rating Curve= 0 ,0
Exp/Cntr=0.3,0.1

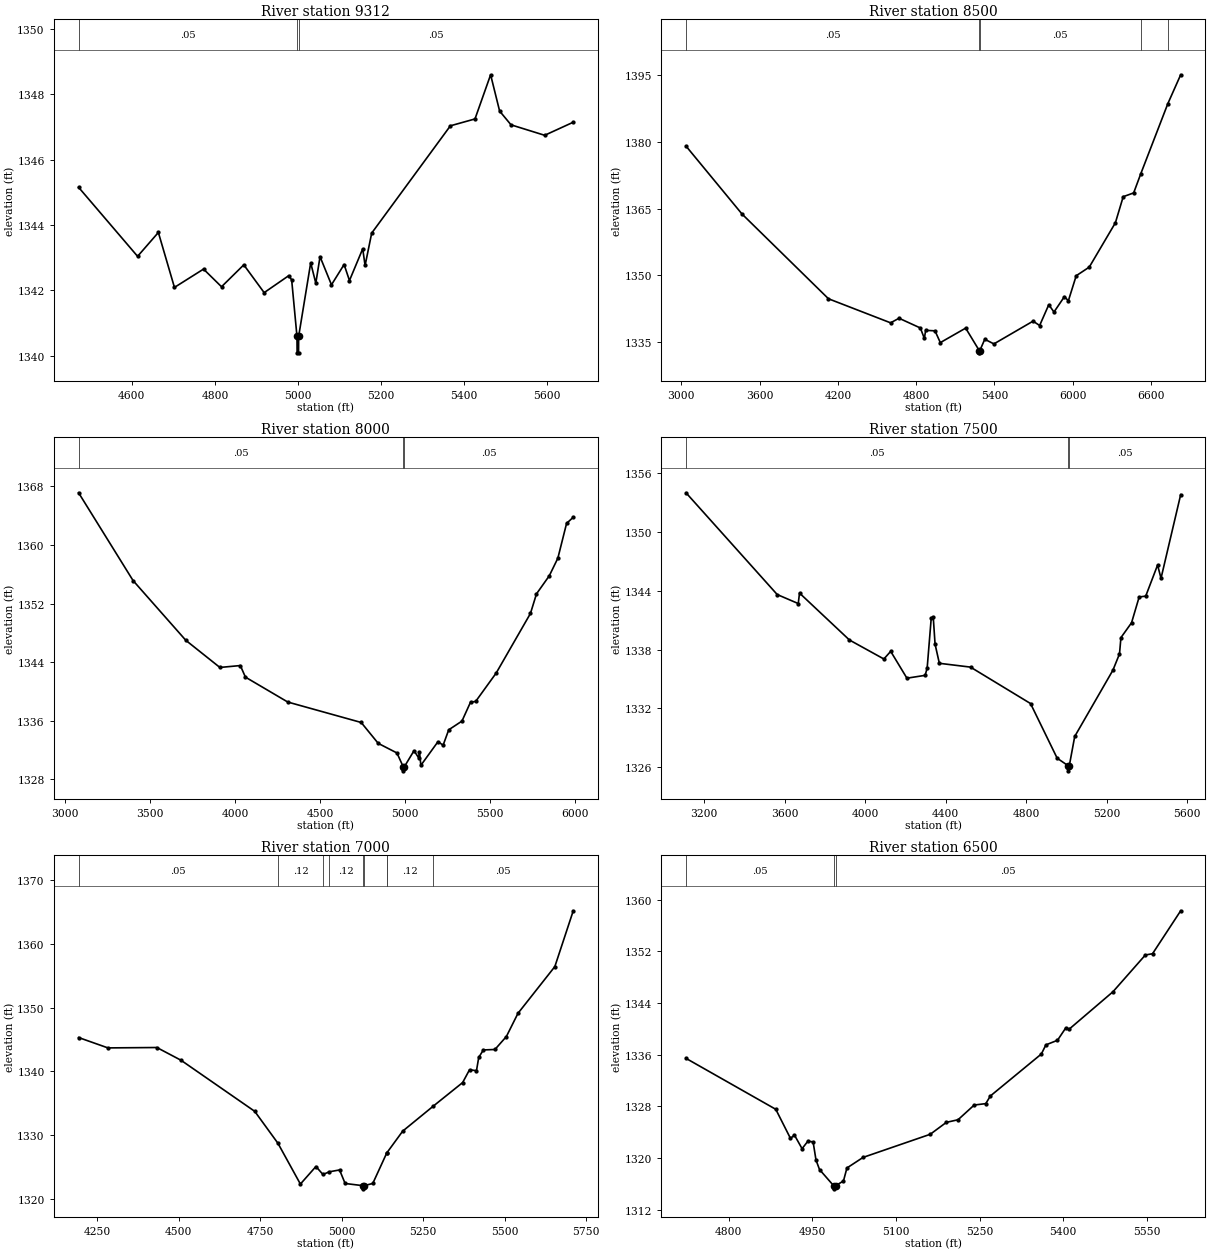
Type RM Length L Ch R = 1 ,9312    ,812,812,812
BEGIN DESCRIPTION:
Mapping XS 297b8605
END DESCRIPTION:
XS GIS Cut Line= 3
      2762988.31     10278975.09      2762988.31     10278740.71
      2762154.98     10278271.96
#Sta/Elev= 30
  4471.8 1345.15  4613.8 1343.04  4663.8 1343.77  4702.5 1342.09  4772.5 1342.65
  4815.8 1342.11  4869.4 1342.78  4918.4 1341.93  4977.7 1342.45  4984.6 1342.32
  4997.4 1340.59  4997.7 1340.09  5001.2 1340.09  5001.4 1340.59  5030.4 1342.84
  5042.7 1342.22  5052.9 1343.03  5080.4 1342.17  5110.8 1342.79  5123.7  1342.3
  5155.6 1343.27  5161.3 1342.76  5177.2 1343.75  5366.6 1347.03  5425.8 1347.24
  5463.4 1348.59  5485.1 1347.48  5512.5 1347.06  5593.5 1346.74  5662.3 1347.14
#Mann= 3 ,-1 , 0
  4471.8     .05       0  4997.4     .05       0  5001.4     .05       0
Bank Sta=4997.4,5001.4
XS Rating Curve= 0 ,0
Exp/Cntr=0.3,0.1

Type RM Length L Ch R = 1 ,8500    ,500,500,500
BEGIN DESCRIPTION:
SANFERNANDO037 17.0
END DESCRIPTION:
XS GIS Cut Line= 3
      2763455.69     10280103.14       2763061.5      10278178.7
      2763155.68     10276353.13
#Sta/Elev= 30
  3035.6 1379.05  3464.4 1363.79  4127.9 1344.71    4604  1339.3  4668.9 1340.33
  4832.2 1338.14  4862.8  1335.8    4873 1337.61  4944.5  1337.5  4985.3 1334.85
  5179.5 1338.11    5284 1333.05  5284.2 1332.55    5288 1333.05    5326  1335.6
  5396.1 1334.56  5696.5 1339.68  5746.6 1338.69  5816.7 1343.37  5856.7 1341.73
  5936.8  1345.2  5966.9 1344.25    6027 1349.89  6127.1 1351.83  6327.4  1361.8
  6387.4 1367.67  6467.5 1368.52  6522.4 1372.85  6729.9 1388.62    6828 1395.09
#Mann= 5 ,-1 , 0
  3035.6     .05       0    5284     .05       0    5288     .05       0
  6522.4     .12       0  6729.9     .05       0
Bank Sta=5284,5288
XS Rating Curve= 0 ,0
Exp/Cntr=0.3,0.1

Type RM Length L Ch R = 1 ,8000    ,500,500,500
BEGIN DESCRIPTION:
SANFERNANDO037 16.0
END DESCRIPTION:
XS GIS Cut Line= 3
      2763455.68     10279753.13      2763370.08     10277834.93
      2763255.68     10276853.08
#Sta/Elev= 30
  3079.9 1367.12  3400.2 1355.14  3710.5 1346.98  3910.7 1343.28  4030.9 1343.54
  4060.9 1341.96  4309.8 1338.56  4741.6 1335.77  4841.7 1332.92  4951.8 1331.61
  4989.8 1329.67  4990.1 1329.17  4993.8 1329.67  5052.2 1331.92  5079.3 1330.95
  5084.3 1331.74  5092.4 1329.92  5193.1 1333.15  5223.3 1332.67  5256.3 1334.77
  5334.1 1335.96  5384.4 1338.54  5414.6 1338.64  5535.4 1342.52  5736.8 1350.65
  5772.2 1353.32  5847.5 1355.79  5897.9 1358.19  5949.2 1362.94  5988.5 1363.78
#Mann= 3 ,-1 , 0
  3079.9     .05       0  4989.8     .05       0  4993.8     .05       0
Bank Sta=4989.8,4993.8
XS Rating Curve= 0 ,0
Exp/Cntr=0.3,0.1

Type RM Length L Ch R = 1 ,7500    ,500,500,500
BEGIN DESCRIPTION:
SANFERNANDO037 15.0
END DESCRIPTION:
XS GIS Cut Line= 3
      2763505.68     10279403.15      2763726.56      10277525.4
      2763505.67     10277003.08
#Sta/Elev= 30
  3109.3 1354.02  3562.4 1343.63    3667 1342.71  3673.2 1343.78  3921.2 1338.99
  4092.4 1337.05  4126.3 1337.83  4206.9 1335.09  4297.5 1335.38  4307.5 1336.13
  4327.7 1341.23  4337.8 1341.31  4346.7 1338.57    4368 1336.61  4522.9 1336.22
  4821.1  1332.5  4953.4 1326.92  5009.5 1326.13  5009.7 1325.63  5013.5 1326.13
  5040.6 1329.14  5230.5 1335.91  5263.1 1337.57  5270.2 1339.23    5323 1340.75
  5360.8 1343.38  5393.4 1343.47  5452.3 1346.64  5469.4 1345.29  5567.1 1353.83
#Mann= 3 ,-1 , 0
  3109.3     .05       0  5009.5     .05       0  5013.5     .05       0
Bank Sta=5009.5,5013.5
XS Rating Curve= 0 ,0
Exp/Cntr=0.3,0.1

Type RM Length L Ch R = 1 ,7000    ,500,500,500
BEGIN DESCRIPTION:
SANFERNANDO037 14.0
END DESCRIPTION:
XS GIS Cut Line= 3
      2764955.65     10277353.11      2764148.97     10277314.45
      2763655.68      10276803.1
#Sta/Elev= 30
  4192.4 1345.31  4282.5 1343.68  4432.6 1343.74  4506.7 1341.74    4733 1333.71
  4804.2 1328.69  4873.1 1322.28  4920.8 1325.04  4942.3 1323.79  4962.1 1324.21
  4993.3  1324.5  5010.4 1322.37    5065 1322.03  5065.2 1321.53    5069 1322.03
  5095.3 1322.38  5138.3 1327.18  5138.6  1327.2  5187.1  1330.6  5281.2 1334.54
    5371 1338.23  5392.1 1340.24  5413.5  1340.1  5420.4 1342.18  5434.6 1343.36
  5470.1 1343.43  5505.3 1345.47  5540.8 1349.11    5654 1356.46  5710.5 1365.23
#Mann= 9 ,-1 , 0
  4192.4     .05       0  4804.2     .12       0  4942.3     .05       0
  4962.1     .12       0    5065     .07       0    5069     .12       0
  5138.3     .05       0  5138.6     .12       0  5281.2     .05       0
Bank Sta=5065,5069
XS Rating Curve= 0 ,0
Exp/Cntr=0.3,0.1

Type RM Length L Ch R = 1 ,6500    ,500,500,500
BEGIN DESCRIPTION:
SANFERNANDO037 13.0
END DESCRIPTION:
XS GIS Cut Line= 3
      2764655.69     10277003.11      2764389.95     10276925.64
      2763905.66      10276553.1
#Sta/Elev= 30
  4723.2 1335.43  4884.3 1327.54  4910.7 1323.03  4917.8 1323.55  4931.5 1321.44
  4941.9  1322.6  4951.3 1322.49  4956.5 1319.68  4962.8 1318.21    4988 1315.72
  4988.2 1315.22    4992 1315.72  5005.8 1316.44    5012 1318.45    5041 1320.09
  5161.5 1323.67  5190.5 1325.52  5211.4 1325.92  5240.4  1328.2  5261.2 1328.42
  5269.4  1329.6  5360.9  1336.1  5369.1 1337.52  5389.9 1338.23  5404.4  1340.1
  5410.7 1339.94  5489.5 1345.75  5547.6 1351.44  5560.5 1351.64    5611 1358.29
#Mann= 3 ,-1 , 0
  4723.2     .05       0    4988     .05       0    4992     .05       0
Bank Sta=4988,4992
XS Rating Curve= 0 ,0
Exp/Cntr=0.3,0.1

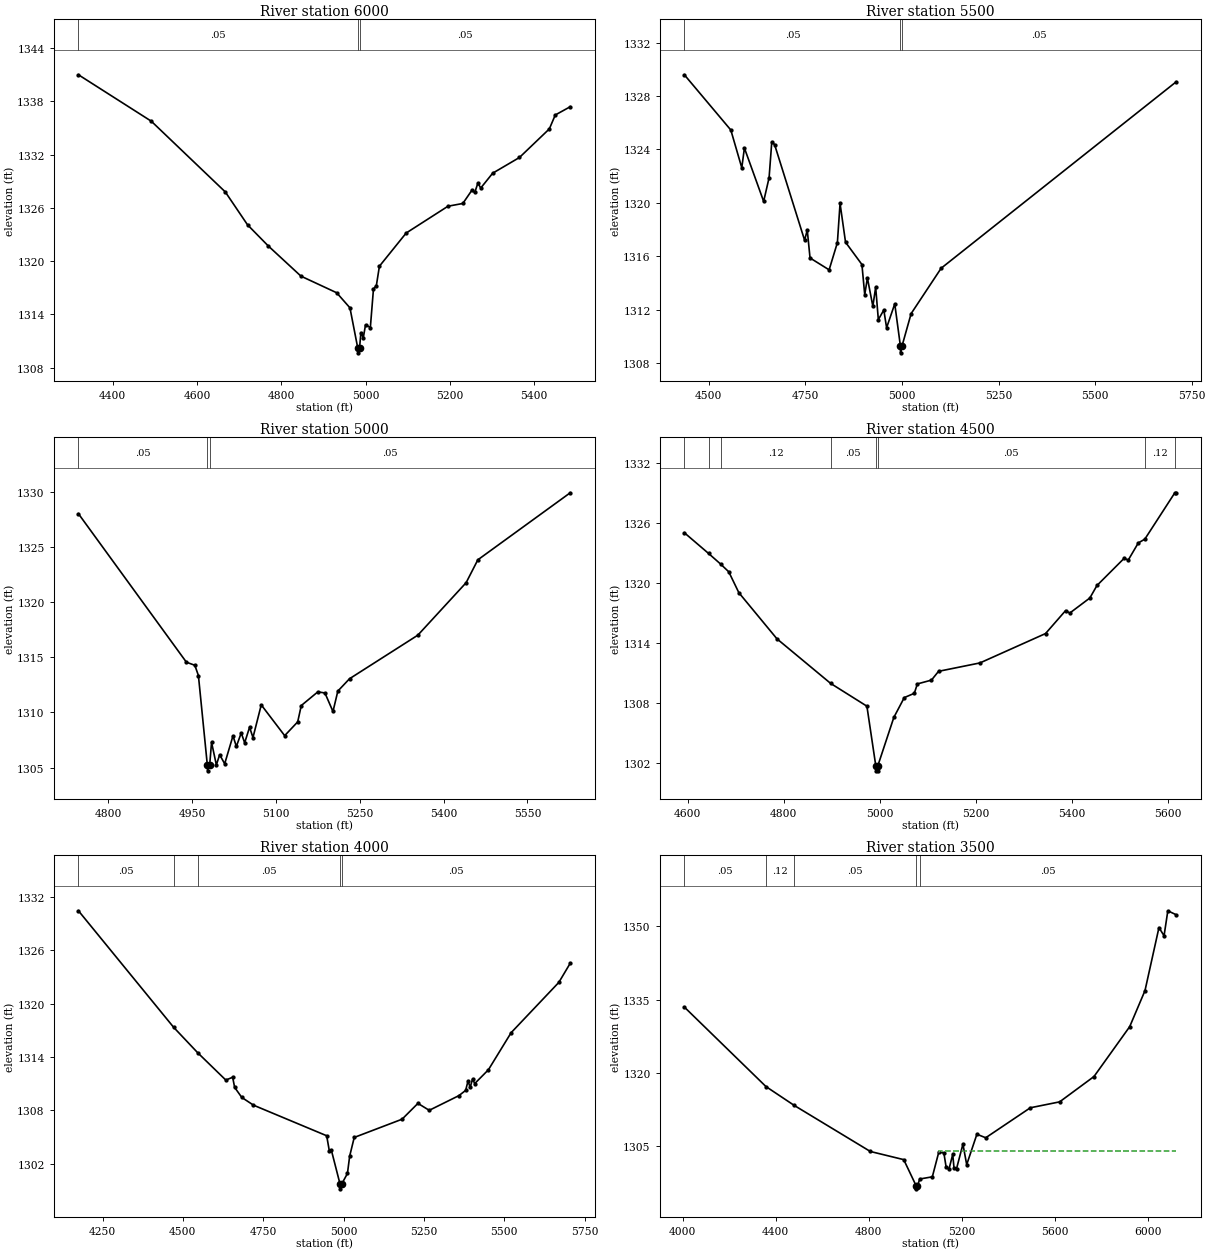
Type RM Length L Ch R = 1 ,6000    ,500,500,500
BEGIN DESCRIPTION:
SANFERNANDO037 12.0
END DESCRIPTION:
XS GIS Cut Line= 3
      2764805.68     10277153.09      2764587.04     10276508.03
      2764255.65     10276153.08
#Sta/Elev= 30
  4318.9 1341.01  4491.7 1335.78  4667.3 1327.81  4720.1  1324.1  4769.1 1321.73
  4846.8 1318.32  4931.5 1316.45    4963 1314.75  4981.7 1310.18    4982 1309.68
  4985.7 1310.18    4989 1311.96  4994.6 1311.36    5000 1312.84  5011.4 1312.53
  5018.8 1316.88  5025.6 1317.24  5032.9 1319.44  5096.4 1323.18  5195.6  1326.2
  5230.8 1326.51  5252.3    1328  5259.1 1327.75  5266.5  1328.8  5273.3 1328.25
  5301.6 1329.92  5365.1 1331.69    5436 1334.91  5450.1 1336.48  5485.6 1337.41
#Mann= 3 ,-1 , 0
  4318.9     .05       0  4981.7     .05       0  4985.7     .05       0
Bank Sta=4981.7,4985.7
XS Rating Curve= 0 ,0
Exp/Cntr=0.3,0.1

Type RM Length L Ch R = 1 ,5500    ,500,500,500
BEGIN DESCRIPTION:
SANFERNANDO037 11.0
END DESCRIPTION:
XS GIS Cut Line= 3
      2765405.69     10276753.12      2764996.98     10276365.47
      2764505.65     10275853.08
#Sta/Elev= 30
  4436.7  1329.6    4557 1325.46  4585.4 1322.63  4592.2 1324.11    4642 1320.11
  4656.1 1321.89    4663 1324.56  4670.3 1324.37    4748  1317.2  4754.9 1317.96
  4762.1 1315.87  4811.5 1314.98  4832.9 1317.02  4839.8 1319.96    4854 1317.05
  4896.4 1315.38  4903.7 1313.11  4910.6 1314.37  4924.7 1312.25    4932 1313.68
  4938.9 1311.25  4953.1 1311.97  4960.3 1310.64  4981.4 1312.43  4996.1 1309.26
  4996.3 1308.76  5000.1 1309.26  5023.8  1311.7  5101.5  1315.1  5709.9 1329.07
#Mann= 3 ,-1 , 0
  4436.7     .05       0  4996.1     .03       0  5000.1     .05       0
Bank Sta=4996.1,5000.1
XS Rating Curve= 0 ,0
Exp/Cntr=0.3,0.1

Type RM Length L Ch R = 1 ,5000    ,500,500,500
BEGIN DESCRIPTION:
SANFERNANDO037 10.0
END DESCRIPTION:
XS GIS Cut Line= 3
      2765555.68     10276153.11      2765319.76     10276061.46
      2764805.72     10275703.14
#Sta/Elev= 30
  4746.9 1328.02    4940 1314.56  4955.1 1314.28  4961.5 1313.35  4977.5 1305.21
  4977.8 1304.71  4981.6 1305.21    4985 1307.29  4993.6 1305.25  4999.5 1306.17
  5008.5 1305.35  5023.3 1307.88  5029.4 1306.92  5038.1 1308.15  5044.2 1307.25
    5053 1308.66  5059.1 1307.73  5073.9 1310.69  5115.8  1307.9  5139.1 1309.15
  5145.5 1310.63  5175.1 1311.87  5187.8 1311.77  5202.2 1310.09  5210.9 1311.94
  5231.8 1313.06    5354 1317.01  5440.4 1321.77  5461.3 1323.84  5626.6 1329.92
#Mann= 3 ,-1 , 0
  4746.9     .05       0  4977.5     .05       0  4981.6     .05       0
Bank Sta=4977.5,4981.6
XS Rating Curve= 0 ,0
Exp/Cntr=0.3,0.1

Type RM Length L Ch R = 1 ,4500    ,500,500,500
BEGIN DESCRIPTION:
SANFERNANDO037 9.0
END DESCRIPTION:
XS GIS Cut Line= 3
      2765605.69     10276053.12      2765512.09     10275657.03
       2765155.7     10275153.13
#Sta/Elev= 30
    4593    1325  4643.4 1322.93  4668.4 1321.87  4685.5 1321.09  4706.5    1319
  4785.9 1314.38  4897.7 1309.92  4973.2 1307.64  4991.7 1301.67  4991.9 1301.17
  4995.6 1301.17  4995.9 1301.67  5029.3 1306.52    5051  1308.5  5071.9 1308.93
  5078.3 1309.87  5107.6 1310.25  5122.4 1311.13  5208.6 1311.97  5345.2 1314.91
    5387 1317.21  5395.7 1316.96  5437.5 1318.47  5452.3 1319.72  5508.9 1322.44
  5517.5 1322.27  5538.4 1323.98    5552 1324.36  5614.5    1329  5617.2    1329
#Mann= 8 ,-1 , 0
    4593     .12       0  4643.4     .05       0  4668.4     .12       0
  4897.7     .05       0  4991.7     .05       0  4995.9     .05       0
    5552     .12       0  5614.5     .05       0
Bank Sta=4991.7,4995.9
XS Rating Curve= 0 ,0
Exp/Cntr=0.3,0.1

Type RM Length L Ch R = 1 ,4000    ,500,500,500
BEGIN DESCRIPTION:
SANFERNANDO037 8.0
END DESCRIPTION:
XS GIS Cut Line= 3
      2766405.68     10276153.11      2765918.25     10275487.62
       2765405.7     10275003.12
#Sta/Elev= 30
  4175.1 1330.46  4471.2 1317.36    4546  1314.5  4633.7 1311.42  4654.9 1311.74
  4661.1  1310.6  4683.3 1309.47  4719.7  1308.6  4947.5 1305.16  4955.9 1303.42
  4962.1 1303.53  4989.3 1299.69  4989.6 1299.19  4993.6 1299.69  5012.1 1300.92
    5019 1302.87  5033.2 1304.97    5182 1307.02  5231.4  1308.8  5266.6 1308.02
  5358.8 1309.67  5379.9 1310.26  5387.1  1311.3    5394 1310.61  5401.3 1311.52
  5408.2 1311.03  5450.7 1312.58  5521.4 1316.75  5669.9 1322.41  5705.3 1324.56
#Mann= 5 ,-1 , 0
  4175.1     .05       0  4471.2     .12       0    4546     .05       0
  4989.3     .05       0  4993.6     .05       0
Bank Sta=4989.3,4993.6
XS Rating Curve= 0 ,0
Exp/Cntr=0.3,0.1

Type RM Length L Ch R = 1 ,3500    ,500,500,500
BEGIN DESCRIPTION:
SANFERNANDO037 7.0
END DESCRIPTION:
XS GIS Cut Line= 3
      2766455.68      10276203.1      2766241.72     10275234.35
      2765255.72     10274703.13
#Sta/Elev= 30
  4007.9 1333.45  4358.5 1317.17  4479.9 1313.31  4806.7 1303.88  4950.1 1302.21
  5004.6 1296.73  5004.9 1296.23  5009.1 1296.73  5018.5 1298.24  5072.9 1298.69
  5100.4 1303.71  5122.4 1303.61  5131.8 1300.78  5144.3 1300.24  5160.5 1303.29
  5166.2 1300.42  5176.7 1300.32  5204.3 1305.38  5220.5 1301.19  5264.3 1307.41
  5302.2 1306.69  5493.8 1312.83  5619.6 1314.04  5767.2 1319.23  5920.5 1329.44
  5986.2 1336.82  6046.2 1349.73  6068.1 1348.05  6084.3 1353.17    6120 1352.36
#Mann= 5 ,-1 , 0
  4007.9     .05       0  4358.5     .12       0  4479.9     .05       0
  5004.6     .05       0  5018.5     .05       0
#XS Ineff= 2 , 0
                         5099.43         1304.08
Permanent Ineff=
       F       F
Bank Sta=5004.6,5009.1
XS Rating Curve= 0 ,0
Exp/Cntr=0.3,0.1

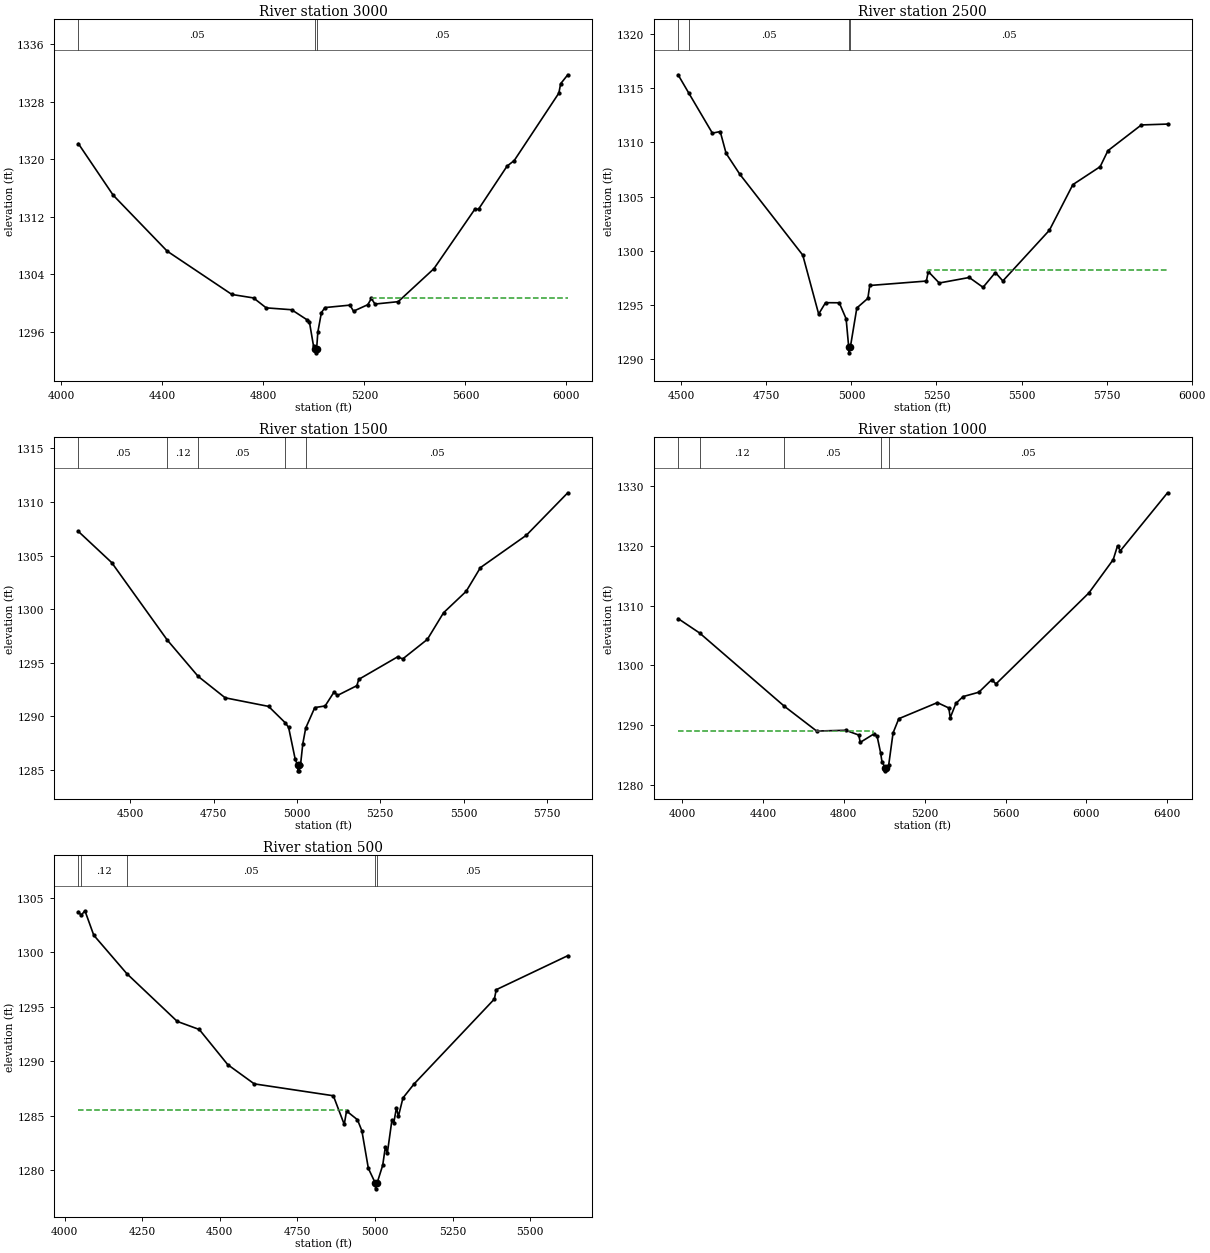
Type RM Length L Ch R = 1 ,3000    ,500,500,500
BEGIN DESCRIPTION:
SANFERNANDO037 6.0
END DESCRIPTION:
XS GIS Cut Line= 3
      2766605.69     10276003.07      2766705.42     10275075.21
       2766005.7     10274353.12
#Sta/Elev= 30
  4066.8 1322.17  4204.8    1315  4418.8 1307.22  4675.1  1301.2  4760.7 1300.72
    4811 1299.34  4911.6 1299.08  4971.9  1297.7    4982 1297.41  4998.5 1294.02
  5006.1 1293.59  5006.4 1293.09  5010.6 1293.59  5015.5 1295.97  5029.7 1298.69
  5043.8 1299.38  5142.6 1299.72  5156.8 1298.88  5213.4 1299.78  5227.5 1300.65
  5241.7 1299.87  5333.7  1300.2  5475.2 1304.78  5637.8 1313.07  5651.9 1313.05
  5765.1 1319.04  5793.4 1319.81  5970.1 1329.18  5977.3 1330.49  6005.5 1331.73
#Mann= 3 ,-1 , 0
  4066.8     .05       0  5006.1     .05       0  5010.6     .05       0
#XS Ineff= 2 , 0
                         5230.11         1300.71
Permanent Ineff=
       F       F
Bank Sta=5006.1,5010.6
XS Rating Curve= 0 ,0
Exp/Cntr=0.3,0.1

Type RM Length L Ch R = 1 ,2500    ,1000,1000,1000
BEGIN DESCRIPTION:
SANFERNANDO037 5.0
END DESCRIPTION:
XS GIS Cut Line= 3
      2767055.68      10275803.1      2766992.89     10275297.69
      2766605.69     10274453.12
#Sta/Elev= 30
  4490.7 1316.26  4521.7 1314.59  4591.5 1310.86  4614.5 1311.01  4631.8 1308.99
  4672.1 1307.06  4857.1 1299.58  4903.8 1294.13    4924 1295.18  4964.3 1295.17
  4984.5 1293.69  4992.2 1291.04  4992.6 1290.54  4996.8 1291.04    5016 1294.69
  5048.4 1295.58  5053.9 1296.77  5220.4 1297.18  5225.9 1298.06  5258.1    1297
  5346.4 1297.51  5386.9  1296.6  5423.1 1297.97  5445.1 1297.19  5581.9 1301.88
  5650.9  1306.1  5731.1 1307.76  5753.9 1309.24  5852.1 1311.62  5929.1  1311.7
#Mann= 4 ,-1 , 0
  4490.7     .12       0  4521.7     .05       0  4992.2     .05       0
  4996.8     .05       0
#XS Ineff= 2 , 0
                         5226.36         1298.21
Permanent Ineff=
       F       F
Bank Sta=4992.2,4996.8
XS Rating Curve= 0 ,0
Exp/Cntr=0.3,0.1

Type RM Length L Ch R = 1 ,1500    ,500,500,500
BEGIN DESCRIPTION:
SANFERNANDO037 3.0
END DESCRIPTION:
XS GIS Cut Line= 3
      2767555.68     10275353.07      2767525.89     10274698.34
      2767105.66     10274003.07
#Sta/Elev= 30
  4344.6 1307.26  4444.7 1304.35    4611 1297.14  4703.9 1293.74    4785 1291.74
  4915.1 1290.94  4965.2 1289.41  4975.2 1288.98  4995.1    1286  5002.8 1285.43
  5003.1 1284.93  5007.2 1284.93  5007.6 1285.43    5011  1285.5  5017.8 1287.46
  5026.5 1288.92  5053.7 1290.83  5084.7 1290.98  5111.9  1292.3  5121.6 1291.96
  5179.8 1292.87  5185.6 1293.46  5302.1 1295.56  5317.6 1295.37  5391.3 1297.19
  5439.8 1299.67  5507.7 1301.67  5550.4 1303.88  5688.2  1306.9  5812.4 1310.86
#Mann= 5 ,-1 , 0
  4344.6     .05       0    4611     .12       0  4703.9     .05       0
  4965.2     .05       0  5026.5     .05       0
Bank Sta=5002.8,5007.6
XS Rating Curve= 0 ,0
Exp/Cntr=0.3,0.1

Type RM Length L Ch R = 1 ,1000    ,500,500,500
BEGIN DESCRIPTION:
SANFERNANDO037 2.0
END DESCRIPTION:
XS GIS Cut Line= 3
      2767555.69     10275403.11      2767934.21     10274456.05
       2766955.7     10273453.12
#Sta/Elev= 30
  3980.1 1307.84  4086.5 1305.42  4506.4 1293.12  4665.6 1288.98  4809.3 1289.11
  4873.9 1288.31    4881 1287.08  4949.3 1288.51  4964.5 1288.13  4981.6 1285.38
  4988.8  1283.8  5005.6 1282.81    5006 1282.31  5010.6 1282.81  5022.2 1283.36
  5043.5 1288.67  5071.8 1291.05  5262.7 1293.75  5319.3 1292.85  5326.3 1291.21
  5354.5 1293.63    5390 1294.76  5467.7 1295.49  5531.5 1297.59  5552.6 1296.88
  6012.2 1312.14  6132.5 1317.72  6153.7 1320.03  6167.8  1319.2  6401.2 1328.93
#Mann= 5 ,-1 , 0
  3980.1     .05       0  4086.5     .12       0  4506.4     .05       0
  4981.6     .05       0  5022.2     .05       0
#XS Ineff= 2 , 0
         4945.45 1288.93
Permanent Ineff=
       F       F
Bank Sta=5005.6,5010.6
XS Rating Curve= 0 ,0
Exp/Cntr=0.3,0.1

Type RM Length L Ch R = 1 ,500     ,0,0,0
BEGIN DESCRIPTION:
SANFERNANDO037 1.0
END DESCRIPTION:
XS GIS Cut Line= 3
      2767655.65     10275303.14       2768363.3      10274660.8
      2768005.68     10274153.11
#Sta/Elev= 30
  4044.3 1303.73  4053.4 1303.41  4065.6 1303.82    4094 1301.58  4200.6 1298.05
    4363 1293.67  4433.9 1292.93  4525.8  1289.7    4611 1287.94  4865.8 1286.85
  4900.9 1284.22  4908.3 1285.45  4943.5 1284.65  4957.7 1283.64  4978.6 1280.19
  5001.4 1278.81  5001.8 1278.31  5006.4 1278.81  5024.8 1280.47  5033.5 1282.18
  5039.6 1281.56  5054.4 1284.59  5060.5 1284.37  5069.2 1285.76  5075.3 1284.95
  5090.1 1286.65  5125.8 1287.93  5384.5 1295.72  5390.6 1296.58    5621  1299.7
#Mann= 5 ,-1 , 0
  4044.3     .05       0  4053.4     .12       0  4200.6     .05       0
  5001.4     .05       0  5006.4     .05       0
#XS Ineff= 2 , 0
         4908.18 1285.54
Permanent Ineff=
       F       F
Bank Sta=5001.4,5006.4
XS Rating Curve= 0 ,0
Exp/Cntr=0.3,0.1

Chan Stop Cuts=-1
Use User Specified Reach Order=0
Composite Channel Slope=5