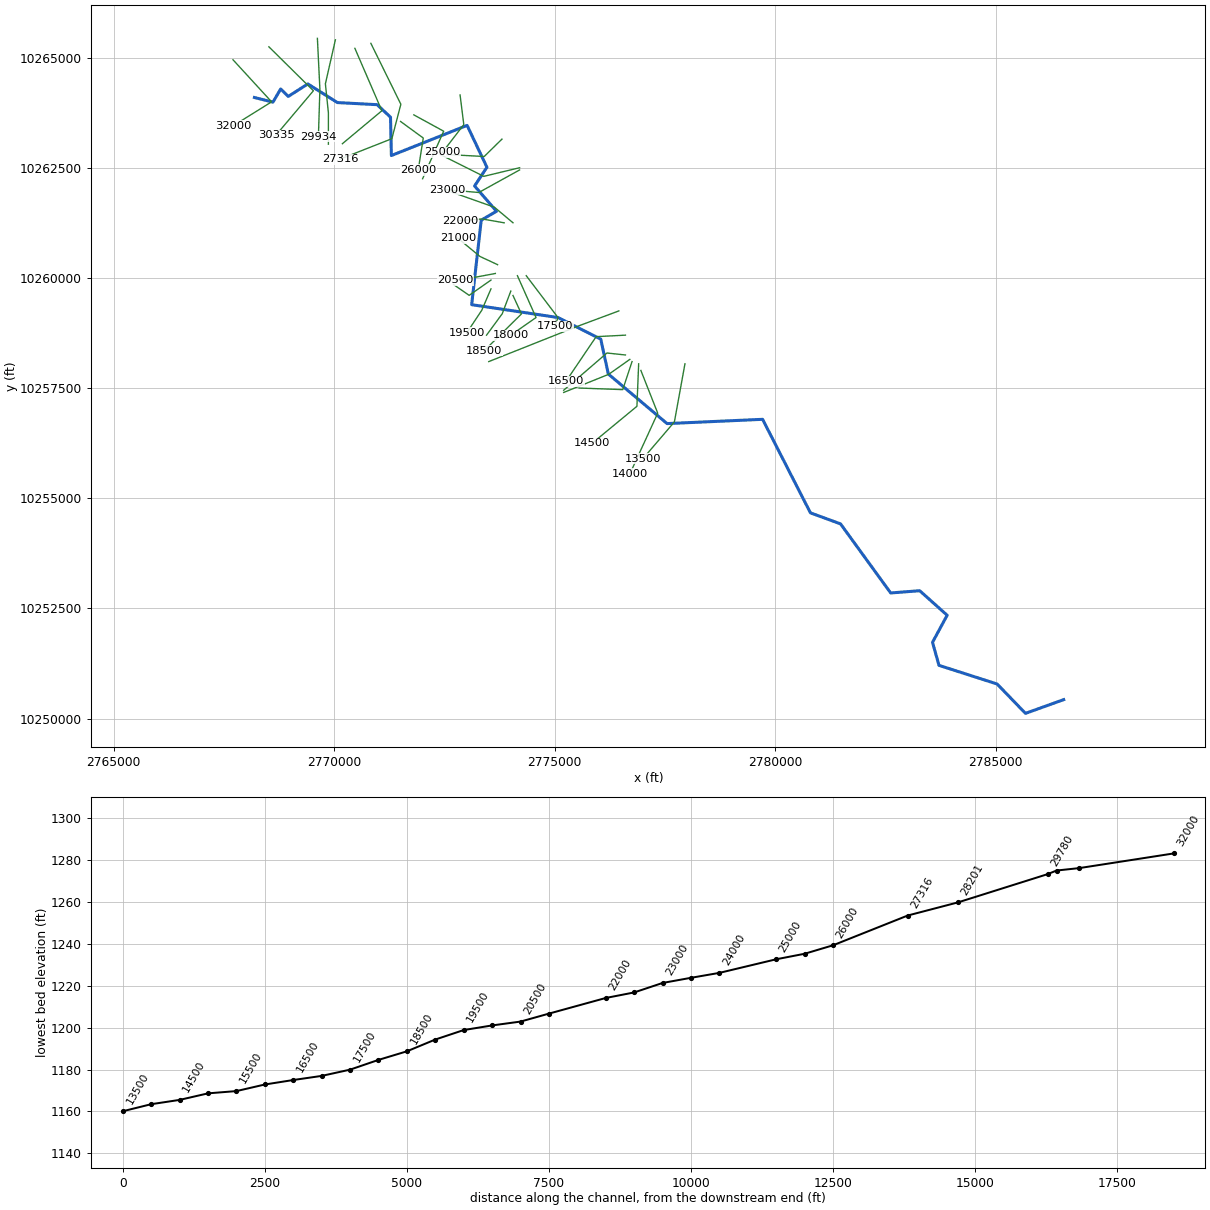
--- SANFERNANDO038.prj (project) ---

Proj Title=SANFERNANDO038 Base Level Engineering
Current Plan=p01
Default Exp/Contr=0.3,0.1
English Units
Geom File=g01
Flow File=f01
Plan File=p01
BEGIN DESCRIPTION:
SANFERNANDO038
END DESCRIPTION:

--- SANFERNANDO038.p01 (plan) ---

Plan Title=Multiple Run
Short Identifier=Multiple
Geom File=g01
Flow File=f01
Subcritical Flow
K Sum by GR= 0
Std Step Tol= 0.01
Critical Tol= 0.01
Num of Std Step Trials= 20
Max Error Tol= 0.3
Flow Tol Ratio= 0.001
Split Flow NTrial= 30
Split Flow Tol= 0.02
Split Flow Ratio= 0.02
Log Output Level= 0
Friction Slope Method= 1
Unsteady Friction Slope Method= 2
Unsteady Bridges Friction Slope Method= 1
Parabolic Critical Depth
Global Vel Dist=  1 , 1 , 1
Global Log Level= 0
CheckData=True
Encroach Param= -1, 0, 0, 0
BEGIN DESCRIPTION:
Multiple Run
END DESCRIPTION:

--- SANFERNANDO038.f01 (steady flow) ---

Flow Title=Multiple
Number of Profiles=7
Profile Names=10-year,25-year,50-year,1pct_min,100-year,1pct_plu,500-year
River Rch & RM= SANFERNANDO038,Reach-1,32000
     467     762     807     505    1049    2182    1405
River Rch & RM= SANFERNANDO038,Reach-1,21000
     920    1563    1895    1115    2546    5812    3415
River Rch & RM= SANFERNANDO038,Reach-1,15500
    1155    1992    2447    1631    3315    6738    4444
River Rch & RM= SANFERNANDO038,Reach-1,11500
    1311    2284    2803    1963    3815    7413    5114
River Rch & RM= SANFERNANDO038,Reach-1,8006
    1493    2619    3320    2203    4546    9378    6092
River Rch & RM= SANFERNANDO038,Reach-1,7000
    1710    3029    3859    2516    5312   11215    7126
River Rch & RM= SANFERNANDO038,Reach-1,3000
    1871    3339    4261    3194    5888   10852    7904
Boundary for River Rch & Prof#=SANFERNANDO038,Reach-1,1
Up Type=0
Dn Type=3
Dn Slope=0.005
Boundary for River Rch & Prof#=SANFERNANDO038,Reach-1,2
Up Type=0
Dn Type=3
Dn Slope=0.005
Boundary for River Rch & Prof#=SANFERNANDO038,Reach-1,3
Up Type=0
Dn Type=3
Dn Slope=0.005
Boundary for River Rch & Prof#=SANFERNANDO038,Reach-1,4
Up Type=0
Dn Type=3
Dn Slope=0.005
Boundary for River Rch & Prof#=SANFERNANDO038,Reach-1,5
Up Type=0
Dn Type=3
Dn Slope=0.005
Boundary for River Rch & Prof#=SANFERNANDO038,Reach-1,6
Up Type=0
Dn Type=3
Dn Slope=0.005
Boundary for River Rch & Prof#=SANFERNANDO038,Reach-1,7
Up Type=0
Dn Type=3
Dn Slope=0.005

--- SANFERNANDO038.g01 (geometry) ---

Geom Title=Existing Conditions

River Reach=SANFERNANDO038,Reach-1
Reach XY= 30
      2768191.50     10264097.00      2768612.00     10263992.00
      2768786.00     10264290.00      2768958.50     10264121.00
      2769402.75     10264405.00      2770072.75     10263982.00
      2770973.75     10263934.00      2771277.75     10263651.00
      2771297.25     10262780.00      2773015.00     10263464.00
      2773464.25     10262514.00      2773184.25     10262089.00
      2773681.25     10261515.00      2773335.00     10261313.00
      2773118.00     10259395.00      2775077.00     10259103.00
      2776045.75     10258613.00      2776217.75     10257821.00
      2777550.25     10256696.00      2779717.00     10256793.00
      2780801.50     10254670.00      2781484.25     10254420.00
      2782621.50     10252852.00      2783279.50     10252903.00
      2783902.75     10252346.00      2783570.50     10251732.00
      2783717.00     10251209.00      2785036.50     10250785.00
      2785678.75     10250119.00      2786545.50     10250431.00

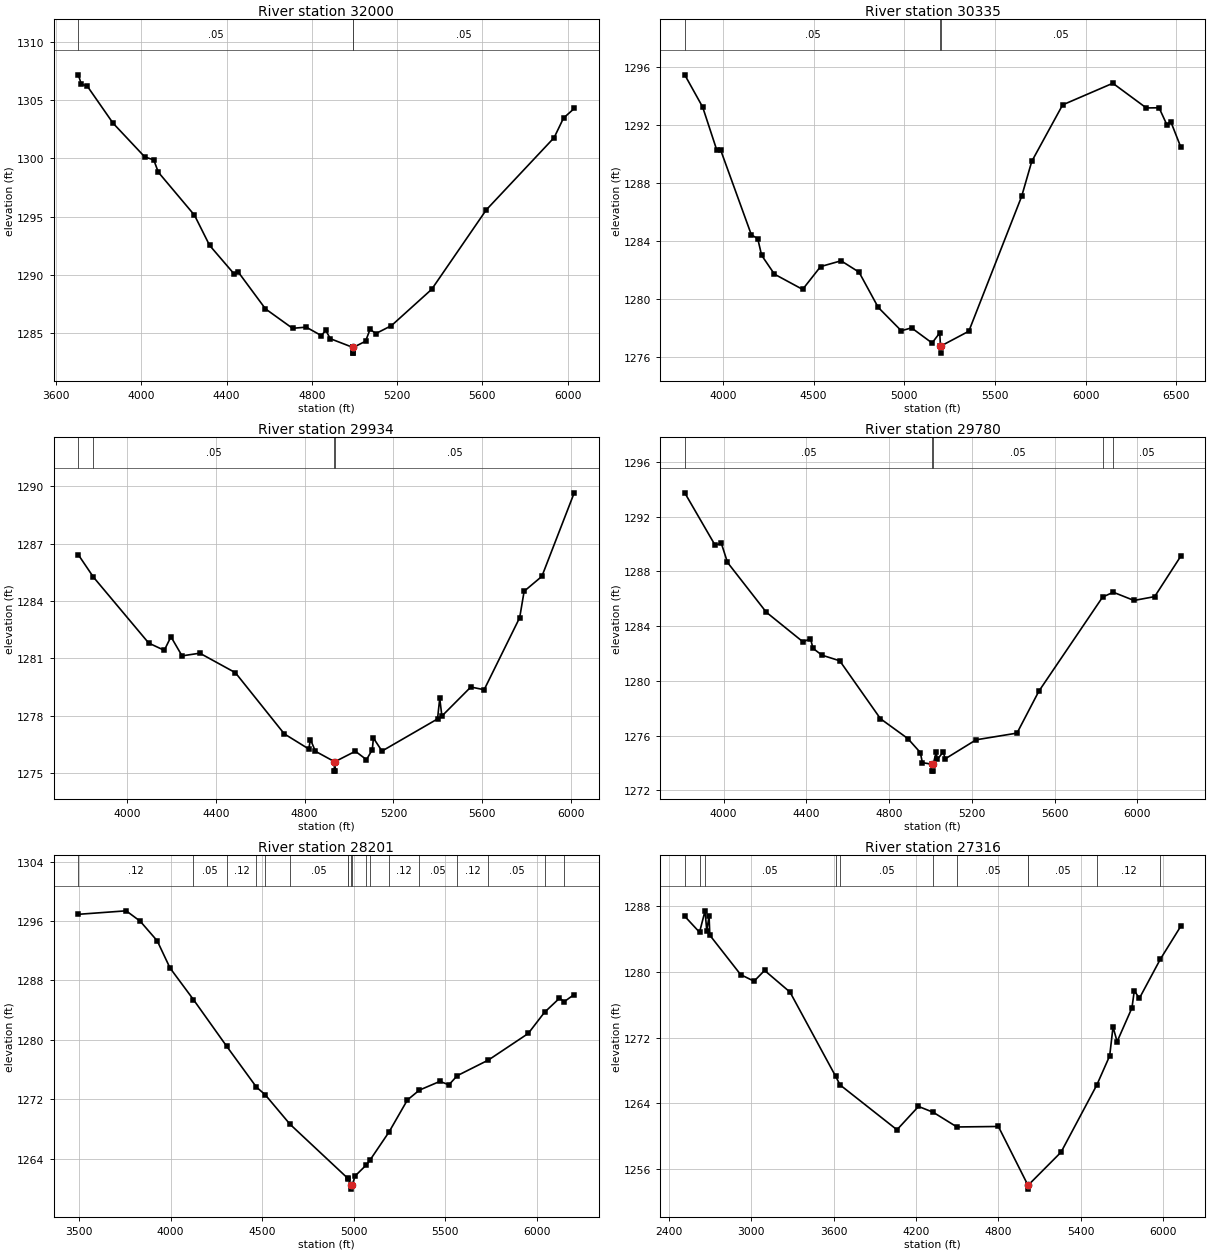
Type RM Length L Ch R = 1,32000,1665,1665,1665
BEGIN DESCRIPTION:
SANFERNANDO038 62.0
END DESCRIPTION:
XS GIS Cut Line= 3
      2767705.67     10264953.13      2768580.67     10263998.31
      2767705.72     10263453.13
#Sta/Elev= 30
  3704.9 1307.18  3718.8 1306.38  3747.2 1306.20  3867.7 1303.03  4016.6 1300.13
  4058.6 1299.88  4080.1 1298.82  4249.7 1295.13  4320.6 1292.54  4434.1 1290.12
  4455.0 1290.25  4582.7 1287.09  4709.7 1285.42  4773.8 1285.52  4844.3 1284.80
  4865.7 1285.24  4886.7 1284.53  4991.4 1283.79  4991.6 1283.29  4995.1 1283.29
  4995.4 1283.79  5052.1 1284.31  5073.3 1285.33  5100.5 1284.97  5173.6 1285.65
  5362.4 1288.77  5618.5 1295.59  5936.7 1301.79  5980.8 1303.47  6030.9 1304.29
#Mann=3,-1,0
  3704.9    0.05       0  4991.4    0.05       0  4995.4    0.05       0
Bank Sta=4991.4,4995.4
Exp/Cntr=0.3,0.1

Type RM Length L Ch R = 1,30335,401,401,401
BEGIN DESCRIPTION:
Mapping XS 1b28b4e5
END DESCRIPTION:
XS GIS Cut Line= 3
      2768519.88     10265247.18      2769528.64     10264249.74
      2768679.60     10263242.20
#Sta/Elev= 30
  3788.5 1295.44  3887.4 1293.22  3965.2 1290.26  3986.4 1290.27  4156.1 1284.42
  4191.4 1284.15  4212.7 1283.01  4283.4 1281.71  4439.0 1280.66  4538.0 1282.23
  4651.1 1282.63  4750.1 1281.85  4856.1 1279.42  4983.4 1277.81  5040.0 1278.01
  5153.1 1276.97  5195.6 1277.66  5199.5 1276.77  5199.8 1276.27  5203.5 1276.77
  5356.1 1277.78  5647.3 1287.06  5703.4 1289.48  5873.7 1293.37  6150.7 1294.86
  6335.3 1293.16  6405.8 1293.17  6448.5 1292.01  6470.6 1292.21  6524.7 1290.49
#Mann=3,-1,0
  3788.5    0.05       0  5199.5    0.05       0  5203.5    0.05       0
Bank Sta=5199.5,5203.5
Exp/Cntr=0.3,0.1

Type RM Length L Ch R = 1,29934,154,154,154
BEGIN DESCRIPTION:
Mapping XS a1c1584b
END DESCRIPTION:
XS GIS Cut Line= 3
      2769619.32     10265439.87      2769675.99     10264283.75
      2769642.01     10263207.49
#Sta/Elev= 30
  3780.5 1286.42  3848.5 1285.25  4097.6 1281.80  4167.7 1281.42  4197.8 1282.13
  4247.8 1281.13  4327.9 1281.27  4488.1 1280.25  4708.4 1277.05  4818.5 1276.26
  4826.5 1276.75  4848.5 1276.14  4933.8 1275.60  4934.1 1275.10  4937.6 1275.10
  4937.8 1275.60  5028.7 1276.14  5078.7 1275.70  5105.0 1276.22  5110.0 1276.83
  5148.7 1276.15  5398.9 1277.83  5408.9 1278.91  5418.5 1277.98  5548.9 1279.50
  5609.0 1279.36  5769.1 1283.13  5789.1 1284.51  5869.1 1285.29  6014.8 1289.66
#Mann=4,-1,0
  3780.5    0.12       0  3848.5    0.05       0  4933.8    0.05       0
  4937.8    0.05       0
Bank Sta=4933.8,4937.8
Exp/Cntr=0.3,0.1

Type RM Length L Ch R = 1,29780,1579,1579,1579
BEGIN DESCRIPTION:
Mapping XS 436e609c
END DESCRIPTION:
XS GIS Cut Line= 4
      2770027.36     10265405.83      2769800.67     10264408.43
      2769868.68     10263751.03      2769868.68     10263037.58
#Sta/Elev= 30
  3812.4 1293.75  3958.8 1289.93  3989.5 1290.05  4019.1 1288.66  4206.7 1285.02
  4384.2 1282.85  4420.2 1283.09  4432.4 1282.38  4475.4 1281.88  4561.6 1281.47
  4758.7 1277.23  4890.9 1275.78  4951.2 1274.76  4961.2 1274.02  5009.5 1273.90
  5009.7 1273.40  5013.2 1273.40  5013.5 1273.90  5028.1 1274.81  5033.2 1274.26
  5061.8 1274.79  5071.8 1274.30  5220.8 1275.69  5418.6 1276.18  5524.1 1279.24
  5832.6 1286.13  5884.2 1286.48  5984.1 1285.88  6084.1 1286.16  6209.6 1289.10
#Mann=5,-1,0
  3812.4    0.05       0  5009.5    0.03       0  5013.5    0.05       0
  5832.6    0.12       0  5884.2    0.05       0
Bank Sta=5009.5,5013.5
Exp/Cntr=0.3,0.1

Type RM Length L Ch R = 1,28201,885,885,885
BEGIN DESCRIPTION:
Mapping XS a82e0cb0
END DESCRIPTION:
XS GIS Cut Line= 3
      2770469.41     10265213.16      2771081.47     10263796.36
      2770186.07     10263048.31
#Sta/Elev= 30
  3495.9 1296.90  3757.4 1297.37  3833.6 1295.98  3927.0 1293.33  3997.0 1289.67
  4125.1 1285.41  4305.7 1279.16  4469.5 1273.62  4516.9 1272.61  4652.7 1268.63
  4967.9 1261.36  4970.4 1261.31  4988.3 1260.39  4988.6 1259.89  4992.3 1260.39
  5008.4 1261.66  5070.1 1263.15  5091.1 1263.84  5194.3 1267.60  5294.4 1271.90
  5359.5 1273.22  5471.8 1274.40  5521.2 1273.94  5566.9 1275.17  5737.4 1277.28
  5954.6 1280.85  6043.6 1283.70  6125.1 1285.59  6152.1 1285.15  6206.0 1286.10
#Mann=18,-1,0
  3495.9    0.12       0  4125.1    0.05       0  4305.7    0.12       0
  4469.5    0.05       0  4516.9    0.12       0  4652.7    0.05       0
  4967.9    0.12       0  4970.4    0.05       0  4988.3    0.05       0
  4992.3    0.05       0  5070.1    0.12       0  5091.1    0.05       0
  5194.3    0.12       0  5359.5    0.05       0  5566.9    0.12       0
  5737.4    0.05       0  6043.6    0.12       0  6152.1    0.05       0
Bank Sta=4988.3,4992.3
Exp/Cntr=0.3,0.1

Type RM Length L Ch R = 1,27316,1316,1316,1316
BEGIN DESCRIPTION:
Mapping XS ddf2dac8
END DESCRIPTION:
XS GIS Cut Line= 4
      2770832.11     10265326.52      2771512.18     10263943.71
      2771308.16     10263161.63      2770131.54     10262697.77
#Sta/Elev= 30
  2515.1 1286.71  2623.0 1284.77  2663.1 1287.37  2675.5 1284.98  2692.4 1286.73
  2698.0 1284.41  2922.7 1279.63  3020.4 1278.83  3096.9 1280.14  3282.3 1277.51
  3614.1 1267.32  3647.1 1266.25  4061.9 1260.81  4218.7 1263.64  4326.3 1262.93
  4498.7 1261.15  4800.8 1261.21  5015.5 1254.11  5015.7 1253.61  5019.5 1254.11
  5257.5 1258.09  5518.2 1266.24  5612.1 1269.78  5636.5 1273.29  5666.2 1271.50
  5774.5 1275.60  5791.4 1277.68  5828.6 1276.76  5981.1 1281.50  6129.1 1285.47
#Mann=11,-1,0
  2515.1    0.05       0  2623.0    0.12       0  2663.1    0.05       0
  3614.1    0.12       0  3647.1    0.05       0  4326.3    0.12       0
  4498.7    0.05       0  5015.5    0.05       0  5019.5    0.05       0
  5518.2    0.12       0  5981.1    0.05       0
Bank Sta=5015.5,5019.5
Exp/Cntr=0.3,0.1

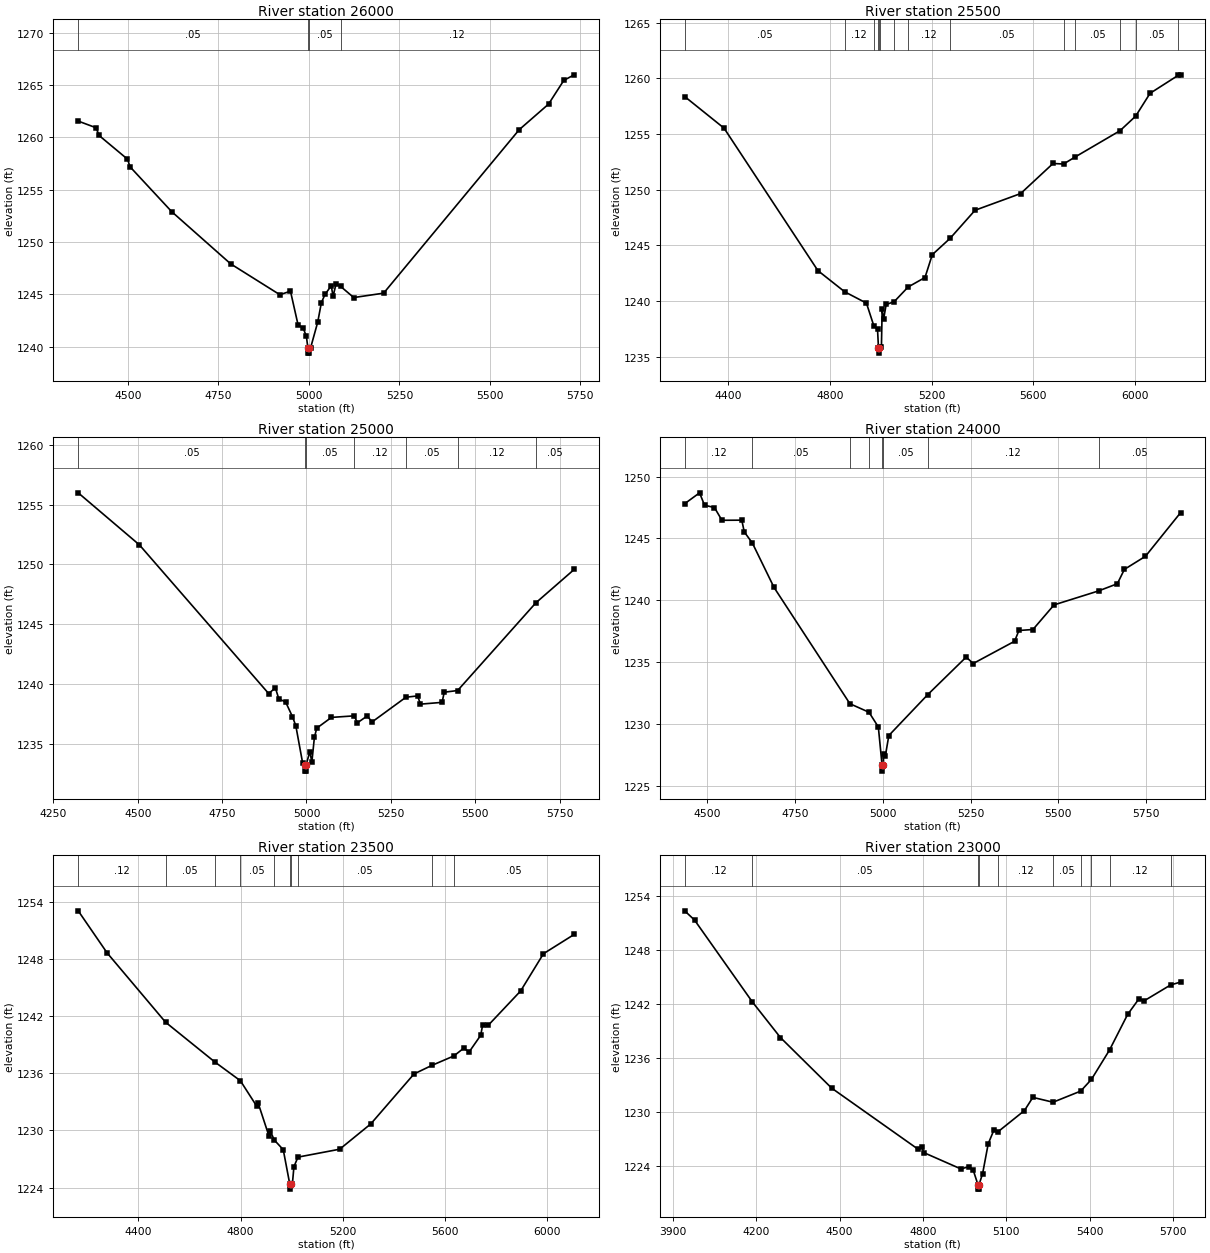
Type RM Length L Ch R = 1,26000,500,500,500
BEGIN DESCRIPTION:
SANFERNANDO038 51.0
END DESCRIPTION:
XS GIS Cut Line= 3
      2771505.68     10263553.12      2772020.64     10263176.99
      2771905.69     10262453.16
#Sta/Elev= 30
  4362.3 1261.54  4411.8 1260.90  4419.8 1260.17  4498.5 1257.90  4505.6 1257.17
  4620.6 1252.89  4783.6 1247.90  4919.6 1244.95  4948.9 1245.29  4969.7 1242.10
  4984.4 1241.73  4992.9 1240.97  4997.0 1239.87  4997.3 1239.37  5000.8 1239.37
  5001.0 1239.87  5004.5 1239.87  5024.2 1242.33  5034.3 1244.19  5044.4 1244.98
  5061.6 1245.81  5066.6 1244.79  5074.8 1245.98  5087.3 1245.75  5123.8 1244.68
  5206.4 1245.10  5581.1 1260.72  5662.1 1263.16  5704.3 1265.43  5732.9 1265.96
#Mann=4,-1,0
  4362.3    0.05       0  4997.0    0.03       0  5001.0    0.05       0
  5087.3    0.12       0
Bank Sta=4997,5001
Exp/Cntr=0.3,0.1

Type RM Length L Ch R = 1,25500,500,500,500
BEGIN DESCRIPTION:
SANFERNANDO038 50.0
END DESCRIPTION:
XS GIS Cut Line= 3
      2771805.71     10263703.10      2772483.06     10263332.31
      2772005.67     10262253.08
#Sta/Elev= 30
  4227.8 1258.36  4382.8 1255.52  4752.2 1242.73  4857.6 1240.83  4943.3 1239.81
  4973.0 1237.73  4986.9 1237.50  4990.6 1235.82  4990.9 1235.32  4994.6 1235.82
  4996.5 1235.85  5002.3 1235.88  5005.2 1239.27  5010.7 1238.35  5021.0 1239.69
  5052.1 1239.93  5107.5 1241.26  5173.8 1242.11  5202.5 1244.16  5272.8 1245.63
  5370.9 1248.15  5550.5 1249.65  5677.9 1252.35  5719.1 1252.30  5764.6 1252.93
  5941.4 1255.29  6003.1 1256.60  6059.8 1258.65  6169.5 1260.25  6180.1 1260.31
#Mann=14,-1,0
  4227.8    0.05       0  4857.6    0.12       0  4973.0    0.05       0
  4990.6    0.07       0  4994.6    0.05       0  4996.5    0.12       0
  5052.1    0.05       0  5107.5    0.12       0  5272.8    0.05       0
  5719.1    0.12       0  5764.6    0.05       0  5941.4    0.12       0
  6003.1    0.05       0  6169.5    0.12       0
Bank Sta=4990.6,4994.6
Exp/Cntr=0.3,0.1

Type RM Length L Ch R = 1,25000,1000,1000,1000
BEGIN DESCRIPTION:
SANFERNANDO038 49.0
END DESCRIPTION:
XS GIS Cut Line= 3
      2772855.68     10264153.12      2772939.72     10263481.76
      2772455.69     10262853.11
#Sta/Elev= 30
  4323.4 1256.00  4504.8 1251.64  4887.8 1239.19  4907.9 1239.66  4918.0 1238.74
  4938.2 1238.48  4958.3 1237.26  4968.4 1236.49  4988.6 1233.37  4994.8 1233.19
  4995.0 1232.69  4998.5 1232.69  4998.8 1233.19  5009.7 1234.31  5016.0 1233.46
  5023.5 1235.53  5030.5 1236.29  5074.0 1237.19  5141.5 1237.32  5151.0 1236.74
  5180.0 1237.31  5194.5 1236.81  5294.8 1238.88  5329.5 1238.99  5337.7 1238.30
  5402.0 1238.45  5408.3 1239.30  5448.0 1239.44  5680.0 1246.79  5793.4 1249.58
#Mann=7,-1,0
  4323.4    0.05       0  4994.8    0.03       0  4998.8    0.05       0
  5141.5    0.12       0  5294.8    0.05       0  5448.0    0.12       0
  5680.0    0.05       0
Bank Sta=4994.8,4998.8
Exp/Cntr=0.3,0.1

Type RM Length L Ch R = 1,24000,500,500,500
BEGIN DESCRIPTION:
SANFERNANDO038 47.0
END DESCRIPTION:
XS GIS Cut Line= 3
      2773805.70     10263153.13      2773402.82     10262758.00
      2772555.72     10262803.11
#Sta/Elev= 30
  4435.7 1247.81  4478.1 1248.69  4492.2 1247.69  4520.5 1247.50  4541.8 1246.47
  4598.4 1246.48  4605.4 1245.53  4628.5 1244.63  4690.2 1241.04  4906.3 1231.64
  4960.7 1230.95  4987.3 1229.76  4997.9 1226.69  4998.2 1226.19  5001.9 1226.69
  5002.1 1227.59  5007.1 1227.39  5017.2 1229.07  5128.2 1232.38  5237.5 1235.41
  5257.5 1234.89  5375.4 1236.69  5387.7 1237.56  5427.7 1237.64  5487.8 1239.63
  5614.6 1240.76  5668.1 1241.34  5688.1 1242.50  5748.2 1243.56  5848.3 1247.09
#Mann=8,-1,0
  4435.7    0.12       0  4628.5    0.05       0  4906.3    0.12       0
  4960.7    0.05       0  4997.9    0.03       0  5001.9    0.05       0
  5128.2    0.12       0  5614.6    0.05       0
Bank Sta=4997.9,5001.9
Exp/Cntr=0.3,0.1

Type RM Length L Ch R = 1,23500,500,500,500
BEGIN DESCRIPTION:
SANFERNANDO038 46.0
END DESCRIPTION:
XS GIS Cut Line= 3
      2774205.73     10262503.12      2773393.50     10262307.30
      2772405.65     10262803.13
#Sta/Elev= 30
  4164.5 1253.04  4277.7 1248.62  4506.3 1241.35  4698.4 1237.19  4799.0 1235.21
  4863.7 1232.51  4868.9 1232.84  4910.8 1229.42  4915.9 1229.97  4931.2 1229.00
  4966.9 1227.97  4992.6 1224.33  4992.8 1223.83  4996.6 1224.33  5002.5 1224.33
  5008.7 1226.19  5024.6 1227.19  5187.8 1228.02  5309.6 1230.68  5478.7 1235.92
  5547.9 1236.81  5634.7 1237.81  5672.5 1238.61  5694.9 1238.25  5739.5 1239.97
  5747.2 1241.06  5769.6 1241.04  5895.9 1244.63  5985.2 1248.54  6105.3 1250.56
#Mann=10,-1,0
  4164.5    0.12       0  4506.3    0.05       0  4698.4    0.12       0
  4799.0    0.05       0  4931.2    0.12       0  4992.6    0.07       0
  4996.6    0.12       0  5024.6    0.05       0  5547.9    0.12       0
  5634.7    0.05       0
Bank Sta=4992.6,4996.6
Exp/Cntr=0.3,0.1

Type RM Length L Ch R = 1,23000,500,500,500
BEGIN DESCRIPTION:
SANFERNANDO038 45.0
END DESCRIPTION:
XS GIS Cut Line= 3
      2774205.72     10262453.13      2773280.42     10261940.94
      2772555.68     10262003.11
#Sta/Elev= 30
  3942.4 1252.40  3977.9 1251.37  4185.6 1242.26  4287.1 1238.27  4471.5 1232.63
  4780.6 1225.86  4796.7 1226.08  4802.4 1225.45  4936.8 1223.62  4965.0 1223.87
  4981.0 1223.48  4997.9 1221.87  4998.1 1221.37  5001.6 1221.37  5001.9 1221.87
  5014.8 1223.11  5034.9 1226.43  5054.9 1227.92  5069.1 1227.74  5165.3 1230.13
  5195.5 1231.60  5268.2 1231.06  5367.7 1232.30  5406.3 1233.60  5471.5 1236.88
  5536.7 1240.85  5576.8 1242.56  5596.9 1242.38  5691.1 1244.13  5727.4 1244.46
#Mann=10,-1,0
  3942.4    0.12       0  4185.6    0.05       0  4997.9    0.05       0
  5001.9    0.05       0  5069.1    0.12       0  5268.2    0.05       0
  5367.7    0.12       0  5406.3    0.05       0  5471.5    0.12       0
  5691.1    0.05       0
Bank Sta=4997.9,5001.9
Exp/Cntr=0.3,0.1

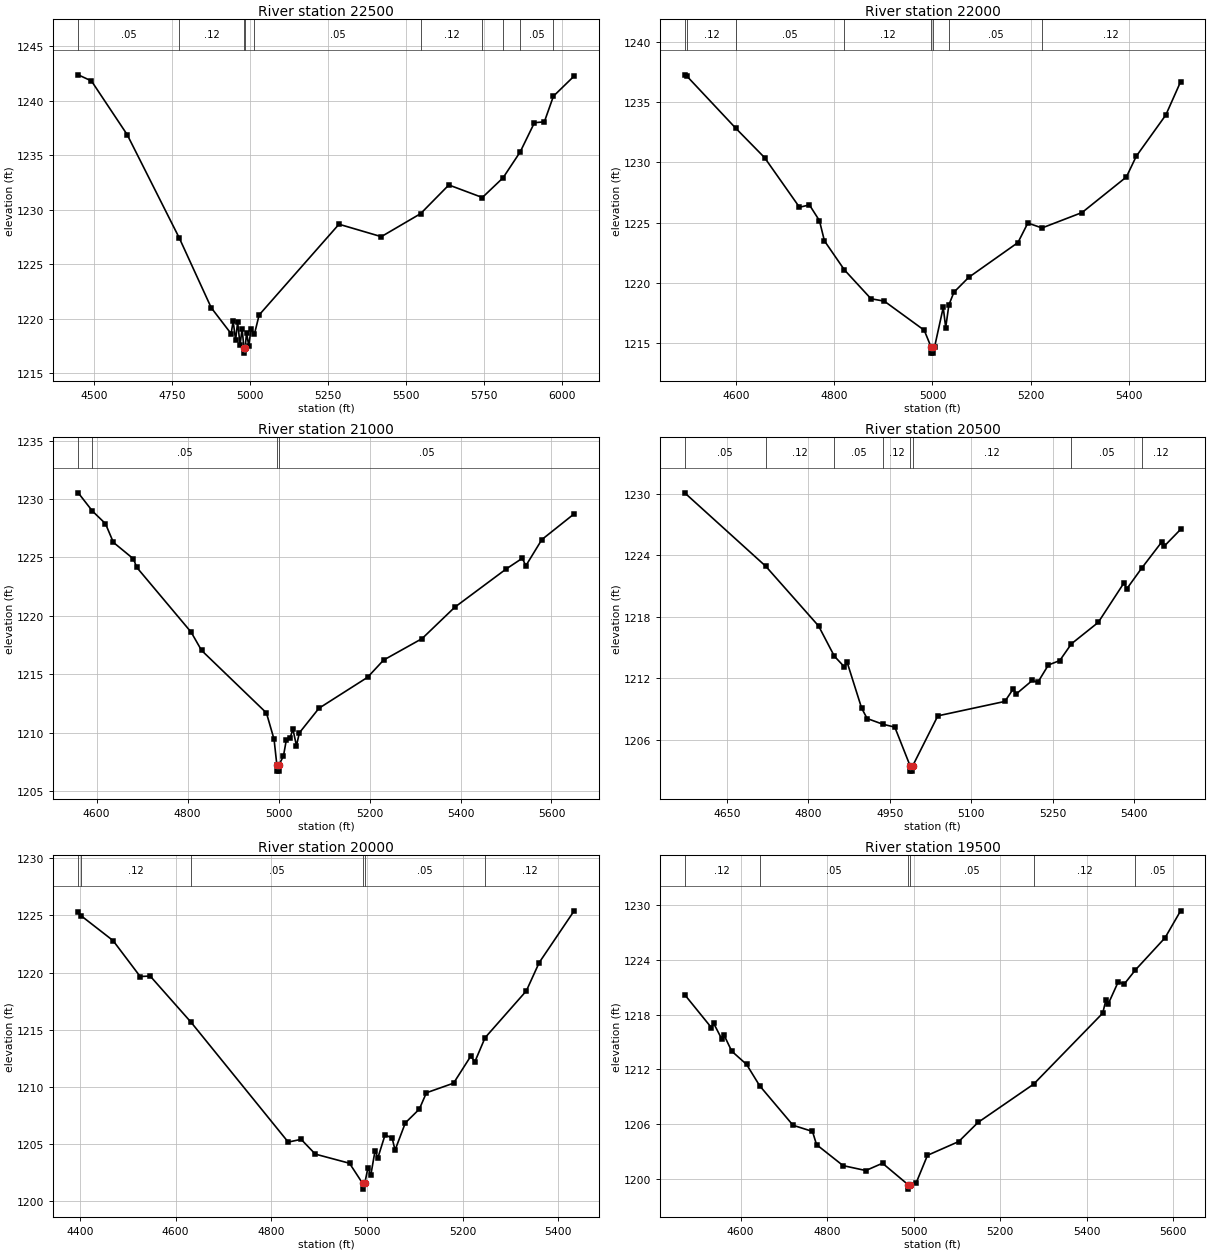
Type RM Length L Ch R = 1,22500,500,500,500
BEGIN DESCRIPTION:
SANFERNANDO038 44.0
END DESCRIPTION:
XS GIS Cut Line= 3
      2774055.65     10261253.14      2773634.32     10261606.97
      2772655.73     10261953.10
#Sta/Elev= 30
  4449.8 1242.36  4492.1 1241.80  4606.5 1236.88  4773.6 1227.39  4875.8 1221.00
  4939.5 1218.62  4946.0 1219.79  4953.8 1218.01  4960.3 1219.70  4968.1 1217.60
  4974.7 1219.08  4980.4 1217.34  4980.7 1216.84  4984.4 1217.34  4989.0 1218.72
  4995.8 1217.51  5003.6 1219.07  5013.9 1218.56  5029.2 1220.34  5284.9 1228.66
  5420.4 1227.52  5546.3 1229.63  5636.7 1232.26  5744.0 1231.11  5810.4 1232.92
  5865.2 1235.29  5910.8 1237.97  5942.6 1238.05  5971.6 1240.40  6038.0 1242.25
#Mann=10,-1,0
  4449.8    0.05       0  4773.6    0.12       0  4980.4    0.07       0
  4984.4    0.12       0  5013.9    0.05       0  5546.3    0.12       0
  5744.0    0.05       0  5810.4    0.12       0  5865.2    0.05       0
  5971.6    0.12       0
Bank Sta=4980.4,4984.4
Exp/Cntr=0.3,0.1

Type RM Length L Ch R = 1,22000,1000,1000,1000
BEGIN DESCRIPTION:
SANFERNANDO038 43.0
END DESCRIPTION:
XS GIS Cut Line= 3
      2773855.69     10261253.11      2773359.13     10261339.95
      2772855.68     10261303.11
#Sta/Elev= 30
  4495.9 1237.27  4500.4 1237.16  4600.3 1232.82  4658.3 1230.41  4729.4 1226.29
  4749.7 1226.48  4770.0 1225.18  4780.2 1223.50  4820.9 1221.09  4874.9 1218.70
  4902.0 1218.50  4983.2 1216.09  4997.2 1214.69  4997.5 1214.19  5001.0 1214.19
  5001.2 1214.69  5004.2 1214.69  5021.9 1217.98  5026.9 1216.31  5033.4 1218.19
  5043.6 1219.24  5073.6 1220.47  5173.9 1223.36  5194.0 1224.98  5222.8 1224.57
  5304.3 1225.85  5394.5 1228.80  5414.6 1230.52  5474.7 1233.94  5504.8 1236.70
#Mann=8,-1,0
  4495.9    0.05       0  4500.4    0.12       0  4600.3    0.05       0
  4820.9    0.12       0  4997.2    0.07       0  5001.2    0.12       0
  5033.4    0.05       0  5222.8    0.12       0
Bank Sta=4997.2,5001.2
Exp/Cntr=0.3,0.1

Type RM Length L Ch R = 1,21000,500,500,500
BEGIN DESCRIPTION:
SANFERNANDO038 42.0
END DESCRIPTION:
XS GIS Cut Line= 3
      2773705.71     10260303.10      2773306.79     10260489.44
      2772805.68     10260903.12
#Sta/Elev= 30
  4559.7 1230.53  4590.9 1228.97  4619.6 1227.89  4637.0 1226.29  4681.1 1224.88
  4688.2 1224.16  4807.9 1218.61  4830.8 1217.05  4973.4 1211.70  4990.2 1209.44
  4996.4 1207.22  4996.6 1206.72  5000.2 1206.72  5000.5 1207.22  5010.8 1208.01
  5017.3 1209.42  5025.1 1209.52  5031.6 1210.31  5039.4 1208.90  5045.9 1210.00
  5088.9 1212.10  5195.8 1214.75  5230.9 1216.22  5315.6 1218.06  5387.3 1220.74
  5500.6 1224.02  5535.8 1224.93  5543.6 1224.29  5578.8 1226.53  5649.8 1228.73
#Mann=4,-1,0
  4559.7    0.12       0  4590.9    0.05       0  4996.4    0.05       0
  5000.5    0.05       0
Bank Sta=4996.4,5000.5
Exp/Cntr=0.3,0.1

Type RM Length L Ch R = 1,20500,500,500,500
BEGIN DESCRIPTION:
SANFERNANDO038 41.0
END DESCRIPTION:
XS GIS Cut Line= 3
      2773655.65     10260103.10      2773235.60     10260024.18
      2772755.73     10259953.12
#Sta/Elev= 30
  4572.6 1230.10  4721.7 1222.93  4819.0 1217.09  4848.0 1214.14  4866.5 1213.09
  4871.6 1213.53  4898.2 1209.06  4908.3 1208.05  4937.3 1207.49  4959.2 1207.21
  4987.5 1203.41  4987.8 1202.91  4991.7 1202.91  4992.0 1203.41  5038.4 1208.31
  5161.7 1209.72  5177.4 1210.96  5182.4 1210.44  5212.2 1211.77  5222.3 1211.58
  5241.8 1213.28  5262.7 1213.71  5284.2 1215.35  5333.5 1217.44  5380.9 1221.30
  5385.9 1220.71  5413.2 1222.72  5450.4 1225.30  5455.4 1224.91  5485.1 1226.53
#Mann=8,-1,0
  4572.6    0.05       0  4721.7    0.12       0  4848.0    0.05       0
  4937.3    0.12       0  4987.5    0.07       0  4992.0    0.12       0
  5284.2    0.05       0  5413.2    0.12       0
Bank Sta=4987.5,4992
Exp/Cntr=0.3,0.1

Type RM Length L Ch R = 1,20000,500,500,500
BEGIN DESCRIPTION:
SANFERNANDO038 40.0
END DESCRIPTION:
XS GIS Cut Line= 3
      2773555.71     10259953.13      2773061.65     10259606.55
      2772705.70     10259853.10
#Sta/Elev= 30
  4396.5 1225.26  4402.5 1224.96  4469.3 1222.79  4526.0 1219.65  4546.9 1219.69
  4632.4 1215.65  4835.4 1205.18  4862.4 1205.42  4892.0 1204.13  4963.5 1203.33
  4990.9 1201.57  4991.2 1201.07  4995.4 1201.57  5002.0 1202.94  5008.0 1202.29
  5016.8 1204.41  5022.9 1203.82  5037.8 1205.81  5052.6 1205.53  5058.7 1204.48
  5080.2 1206.86  5109.4 1208.06  5124.2 1209.49  5181.0 1210.33  5216.8 1212.68
  5225.6 1212.21  5246.8 1214.30  5333.0 1218.39  5360.0 1220.87  5433.0 1225.39
#Mann=6,-1,0
  4396.5    0.05       0  4402.5    0.12       0  4632.4    0.05       0
  4990.9    0.05       0  4995.4    0.05       0  5246.8    0.12       0
Bank Sta=4990.9,4995.4
Exp/Cntr=0.3,0.1

Type RM Length L Ch R = 1,19500,500,500,500
BEGIN DESCRIPTION:
SANFERNANDO038 39.0
END DESCRIPTION:
XS GIS Cut Line= 3
      2773555.69     10259753.12      2773346.88     10259267.07
      2773005.68     10258753.11
#Sta/Elev= 30
  4471.0 1220.20  4532.6 1216.59  4538.0 1217.05  4556.2 1215.38  4561.6 1215.80
  4579.7 1214.00  4614.1 1212.54  4644.3 1210.20  4721.3 1205.87  4766.3 1205.19
  4775.7 1203.74  4837.0 1201.44  4889.5 1200.90  4928.1 1201.70  4986.9 1199.36
  4987.2 1198.86  4991.5 1199.36  5005.4 1199.49  5032.0 1202.57  5104.2 1204.08
  5148.8 1206.18  5277.3 1210.38  5436.9 1218.17  5444.0 1219.56  5450.0 1219.22
  5472.9 1221.62  5486.1 1221.33  5512.6 1222.92  5580.9 1226.44  5616.9 1229.40
#Mann=6,-1,0
  4471.0    0.12       0  4644.3    0.05       0  4986.9    0.03       0
  4991.5    0.05       0  5277.3    0.12       0  5512.6    0.05       0
Bank Sta=4986.9,4991.5
Exp/Cntr=0.3,0.1

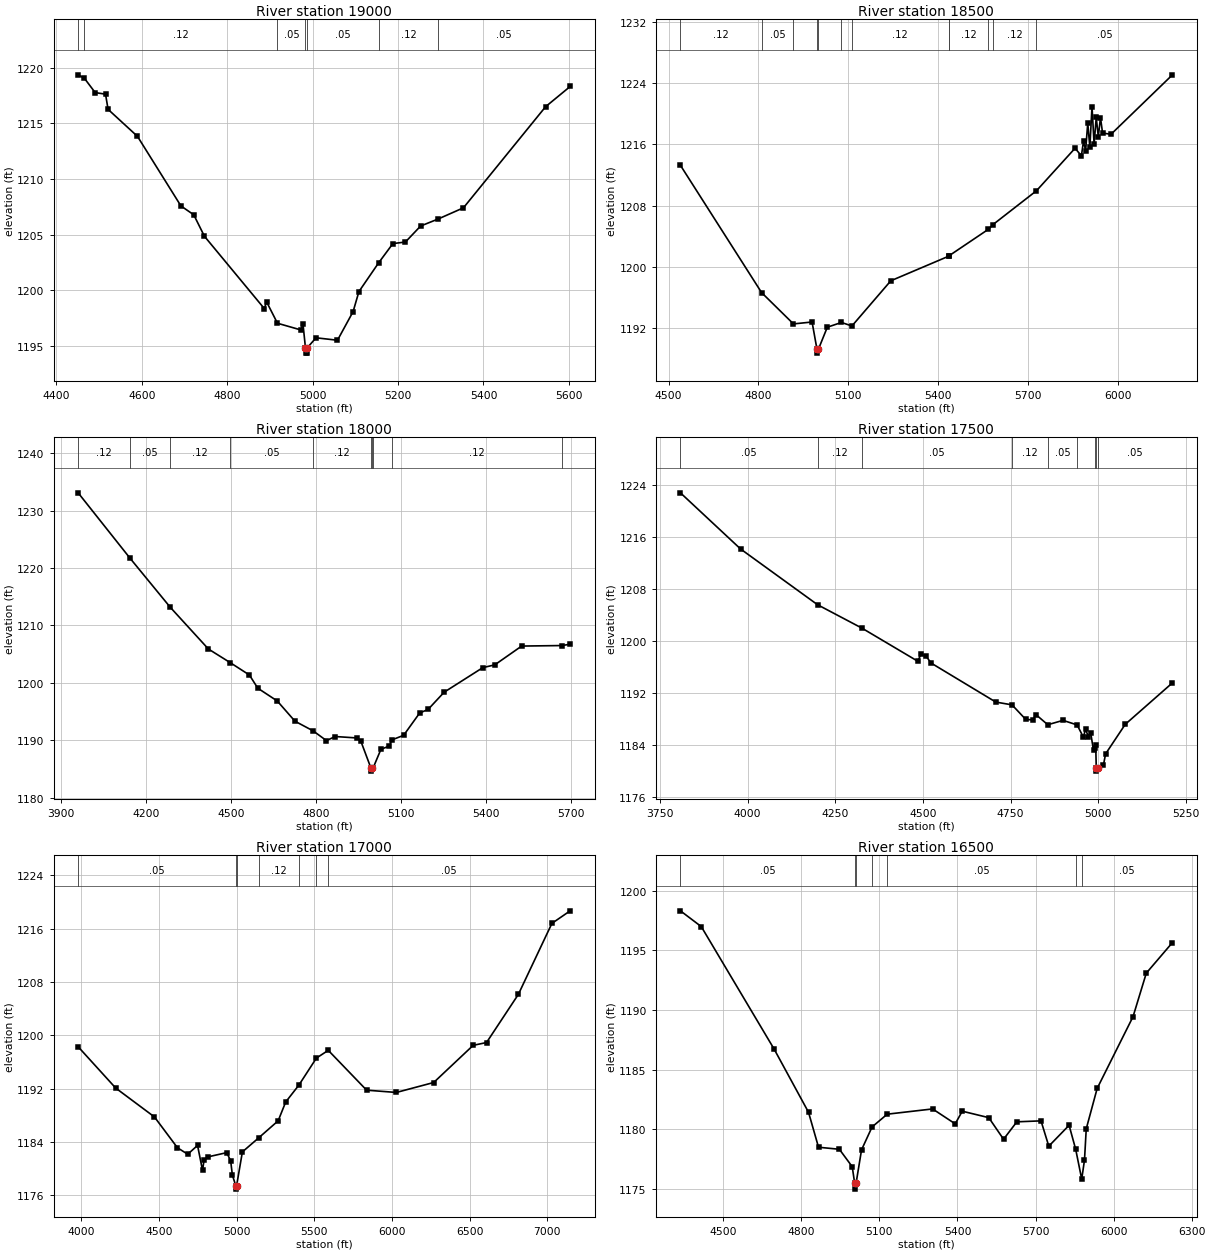
Type RM Length L Ch R = 1,19000,500,500,500
BEGIN DESCRIPTION:
SANFERNANDO038 38.0
END DESCRIPTION:
XS GIS Cut Line= 3
      2774005.68     10259703.10      2773811.80     10259189.58
      2773455.67     10258703.10
#Sta/Elev= 30
  4451.1 1219.38  4465.9 1219.06  4491.0 1217.78  4515.2 1217.64  4521.2 1216.27
  4590.0 1213.84  4691.7 1207.58  4721.8 1206.78  4746.7 1204.85  4886.9 1198.34
  4892.3 1198.94  4917.7 1197.02  4972.2 1196.42  4977.5 1196.93  4983.2 1194.83
  4983.5 1194.33  4987.5 1194.33  4987.9 1194.83  5008.0 1195.71  5058.2 1195.49
  5094.8 1198.07  5108.4 1199.87  5154.6 1202.46  5187.9 1204.19  5217.2 1204.33
  5252.8 1205.77  5294.3 1206.41  5353.1 1207.41  5545.4 1216.51  5602.9 1218.33
#Mann=7,-1,0
  4451.1    0.05       0  4465.9    0.12       0  4917.7    0.05       0
  4983.2    0.03       0  4987.9    0.05       0  5154.6    0.12       0
  5294.3    0.05       0
Bank Sta=4983.2,4987.9
Exp/Cntr=0.3,0.1

Type RM Length L Ch R = 1,18500,500,500,500
BEGIN DESCRIPTION:
SANFERNANDO038 37.0
END DESCRIPTION:
XS GIS Cut Line= 3
      2774055.67     10259603.14      2774247.09     10259184.32
      2773405.71     10258353.14
#Sta/Elev= 30
  4539.5 1213.26  4810.7 1196.61  4917.0 1192.52  4979.2 1192.77  4995.6 1189.20
  4995.9 1188.70  5000.3 1189.20  5030.1 1192.09  5077.3 1192.71  5112.3 1192.25
  5242.2 1198.16  5435.2 1201.37  5436.3 1201.42  5568.3 1204.90  5582.5 1205.48
  5728.6 1209.93  5857.5 1215.49  5878.7 1214.50  5885.8 1216.44  5892.8 1215.16
  5899.9 1218.80  5906.9 1215.61  5914.1 1220.93  5921.1 1216.02  5928.2 1219.52
  5935.2 1217.00  5942.4 1219.50  5949.4 1217.47  5977.7 1217.32  6182.7 1225.09
#Mann=12,-1,0
  4539.5    0.12       0  4810.7    0.05       0  4917.0    0.12       0
  4995.6    0.07       0  5000.3    0.12       0  5077.3    0.05       0
  5112.3    0.12       0  5435.2    0.05       0  5436.3    0.12       0
  5568.3    0.05       0  5582.5    0.12       0  5728.6    0.05       0
Bank Sta=4995.6,5000.3
Exp/Cntr=0.3,0.1

Type RM Length L Ch R = 1,18000,500,500,500
BEGIN DESCRIPTION:
SANFERNANDO038 36.0
END DESCRIPTION:
XS GIS Cut Line= 3
      2774155.68     10260053.13      2774578.39     10259102.80
      2774005.67     10258703.11
#Sta/Elev= 30
  3959.9 1233.09  4144.0 1221.65  4285.2 1213.16  4420.1 1205.88  4497.0 1203.51
  4565.0 1201.35  4594.7 1199.05  4663.5 1196.82  4726.0 1193.30  4790.0 1191.62
  4837.2 1189.92  4868.3 1190.63  4944.9 1190.38  4958.9 1189.81  4994.7 1185.10
  4995.0 1184.60  4999.4 1185.10  5001.7 1185.10  5029.7 1188.39  5059.4 1188.98
  5068.7 1190.04  5110.0 1190.84  5166.7 1194.73  5196.4 1195.35  5253.1 1198.35
  5390.0 1202.64  5431.9 1203.11  5527.0 1206.39  5669.2 1206.48  5698.4 1206.71
#Mann=10,-1,0
  3959.9    0.12       0  4144.0    0.05       0  4285.2    0.12       0
  4497.0    0.05       0  4790.0    0.12       0  4994.7    0.07       0
  4999.4    0.12       0  5001.7    0.05       0  5068.7    0.12       0
  5669.2    0.05       0
Bank Sta=4994.7,4999.4
Exp/Cntr=0.3,0.1

Type RM Length L Ch R = 1,17500,500,500,500
BEGIN DESCRIPTION:
SANFERNANDO038 35.0
END DESCRIPTION:
XS GIS Cut Line= 3
      2774355.69     10260053.11      2775075.38     10259103.27
      2775005.70     10258903.15
#Sta/Elev= 30
  3808.3 1222.82  3979.9 1214.17  4199.5 1205.58  4325.9 1201.98  4485.8 1196.86
  4493.8 1197.92  4508.3 1197.74  4522.9 1196.61  4708.0 1190.58  4754.3 1190.15
  4793.4 1187.91  4814.2 1187.83  4822.5 1188.65  4856.3 1187.09  4899.8 1187.76
  4940.0 1187.06  4957.7 1185.19  4964.0 1186.37  4972.2 1185.26  4978.5 1185.88
  4986.8 1183.16  4990.1 1183.55  4993.1 1183.90  4994.6 1180.44  4994.9 1179.94
  4999.4 1180.44  5015.2 1180.92  5021.3 1182.60  5077.3 1187.15  5211.9 1193.54
#Mann=9,-1,0
  3808.3    0.05       0  4199.5    0.12       0  4325.9    0.05       0
  4754.3    0.12       0  4856.3    0.05       0  4940.0    0.12       0
  4990.1    0.05       0  4994.6    0.05       0  4999.4    0.05       0
Bank Sta=4994.6,4999.4
Exp/Cntr=0.3,0.1

Type RM Length L Ch R = 1,17000,500,500,500
BEGIN DESCRIPTION:
SANFERNANDO038 34.0
END DESCRIPTION:
XS GIS Cut Line= 3
      2776455.67     10259253.11      2775500.26     10258896.48
      2773505.66     10258103.10
#Sta/Elev= 30
  3980.2 1198.29  4221.8 1192.10  4471.2 1187.77  4619.4 1183.15  4685.4 1182.18
  4748.7 1183.50  4780.7 1179.76  4790.6 1181.31  4812.8 1181.77  4936.8 1182.42
  4961.8 1181.17  4972.9 1179.04  4994.9 1177.45  4995.3 1176.95  4999.9 1177.45
  5037.2 1182.53  5143.3 1184.66  5267.4 1187.19  5316.0 1190.01  5400.2 1192.52
  5513.6 1196.59  5589.9 1197.75  5836.7 1191.78  6028.2 1191.44  6268.4 1192.93
  6522.4 1198.50  6608.5 1198.92  6813.3 1206.14  7029.2 1216.78  7146.6 1218.66
#Mann=7,-1,0
  3980.2    0.05       0  4994.9    0.05       0  4999.9    0.05       0
  5143.3    0.12       0  5400.2    0.05       0  5513.6    0.12       0
  5589.9    0.05       0
Bank Sta=4994.9,4999.9
Exp/Cntr=0.3,0.1

Type RM Length L Ch R = 1,16500,500,500,500
BEGIN DESCRIPTION:
SANFERNANDO038 33.0
END DESCRIPTION:
XS GIS Cut Line= 3
      2776605.70     10258703.11      2775941.97     10258669.12
      2775255.67     10257653.10
#Sta/Elev= 30
  4335.4 1198.30  4415.5 1196.98  4695.9 1186.70  4827.7 1181.42  4866.1 1178.49
  4946.2 1178.32  4995.6 1176.86  5005.0 1175.48  5005.4 1174.98  5010.5 1175.48
  5031.4 1178.27  5071.9 1180.19  5130.1 1181.26  5304.5 1181.70  5391.4 1180.45
  5418.4 1181.51  5520.3 1180.97  5577.2 1179.16  5628.2 1180.62  5721.1 1180.70
  5751.0 1178.58  5829.0 1180.33  5854.4 1178.31  5877.5 1175.82  5888.2 1177.42
  5894.9 1180.03  5936.9 1183.42  6074.7 1189.43  6125.7 1193.08  6226.1 1195.64
#Mann=7,-1,0
  4335.4    0.05       0  5005.0    0.05       0  5010.5    0.05       0
  5071.9    0.12       0  5130.1    0.05       0  5854.4    0.12       0
  5877.5    0.05       0
Bank Sta=5005,5010.5
Exp/Cntr=0.3,0.1

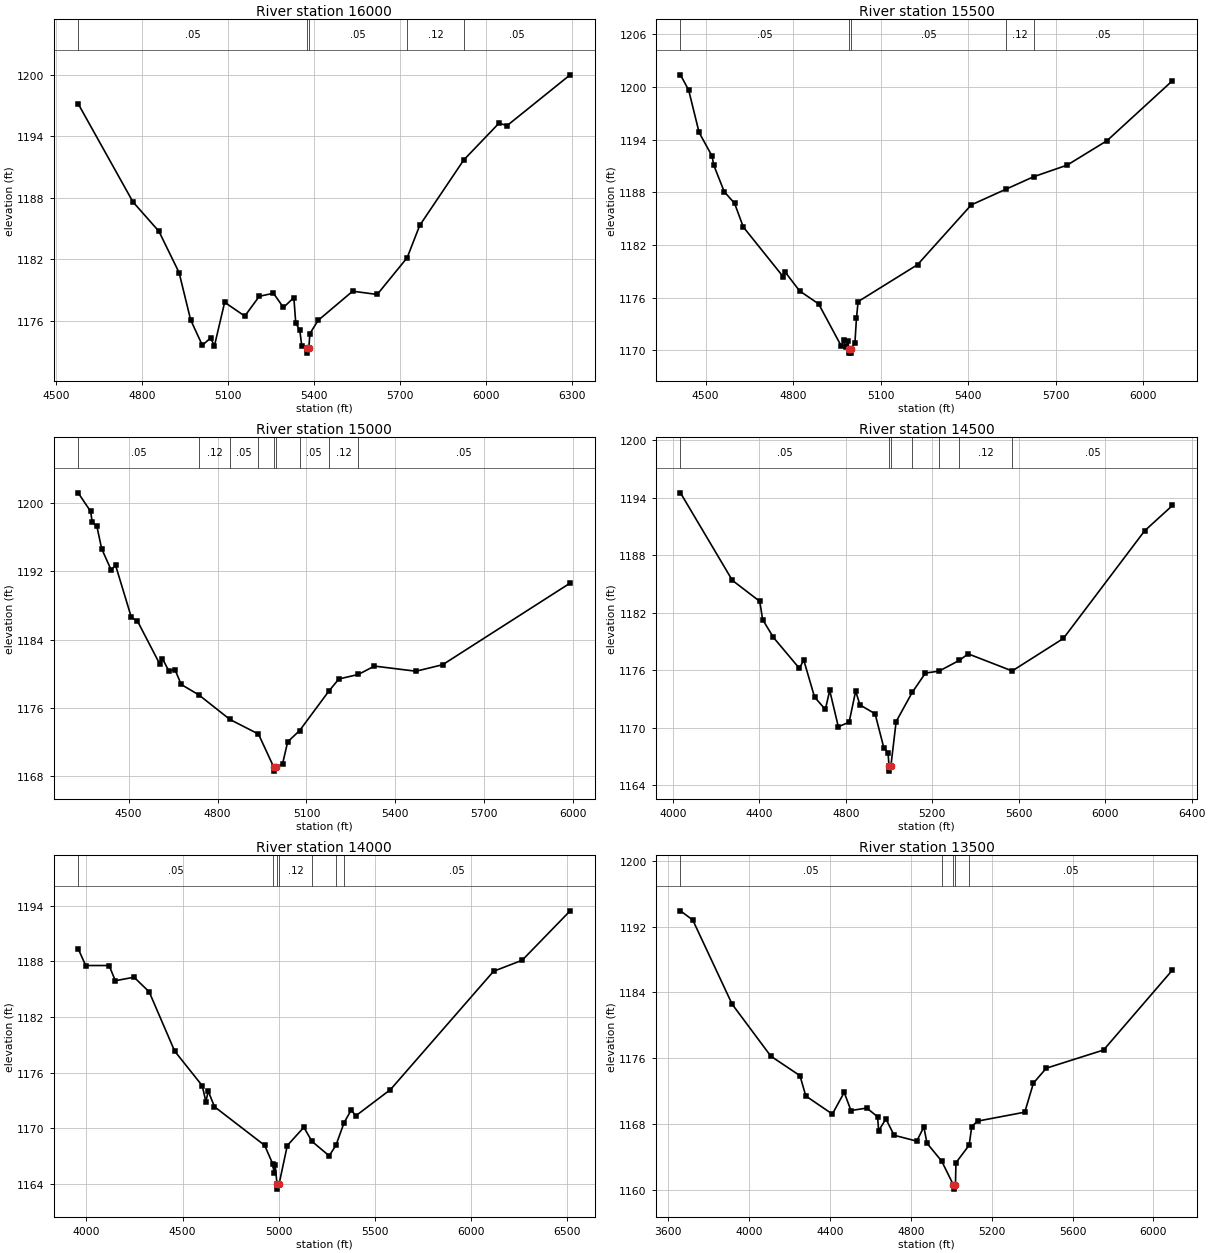
Type RM Length L Ch R = 1,16000,500,500,500
BEGIN DESCRIPTION:
SANFERNANDO038 32.0
END DESCRIPTION:
XS GIS Cut Line= 3
      2776605.73     10258253.11      2776186.33     10258298.05
      2775205.72     10257453.14
#Sta/Elev= 30
  4578.2 1197.16  4769.3 1187.59  4859.9 1184.72  4930.3 1180.69  4970.5 1176.09
  5011.3 1173.61  5039.9 1174.31  5053.7 1173.56  5089.2 1177.80  5159.5 1176.45
  5209.9 1178.38  5259.3 1178.68  5294.4 1177.29  5330.6 1178.26  5337.2 1175.78
  5351.5 1175.05  5358.1 1173.56  5377.2 1173.34  5377.6 1172.84  5382.8 1173.34
  5386.6 1174.75  5415.1 1176.03  5535.8 1178.88  5621.3 1178.56  5725.9 1182.15
  5769.5 1185.29  5923.3 1191.68  6046.0 1195.26  6074.5 1195.03  6294.4 1199.98
#Mann=5,-1,0
  4578.2    0.05       0  5377.2    0.03       0  5382.8    0.05       0
  5725.9    0.12       0  5923.3    0.05       0
Bank Sta=5377.2,5382.8
Exp/Cntr=0.3,0.1

Type RM Length L Ch R = 1,15500,500,500,500
BEGIN DESCRIPTION:
SANFERNANDO038 31.0
END DESCRIPTION:
XS GIS Cut Line= 3
      2776705.68     10258153.11      2776226.92     10257814.50
      2775205.67     10257403.10
#Sta/Elev= 30
  4413.6 1201.40  4441.9 1199.65  4477.6 1194.83  4521.9 1192.15  4528.1 1191.09
  4563.7 1188.09  4599.4 1186.75  4629.0 1184.07  4765.6 1178.41  4771.8 1178.97
  4822.2 1176.78  4887.5 1175.30  4965.0 1170.51  4973.7 1171.13  4979.8 1170.39
  4988.4 1171.04  4990.5 1170.19  4991.0 1169.69  4998.2 1169.69  4998.7 1170.19
  5011.9 1170.79  5017.3 1173.69  5022.9 1175.56  5226.8 1179.77  5411.0 1186.58
  5528.8 1188.35  5624.8 1189.79  5739.8 1191.11  5876.7 1193.90  6101.0 1200.73
#Mann=5,-1,0
  4413.6    0.05       0  4990.5    0.03       0  4998.7    0.05       0
  5528.8    0.12       0  5624.8    0.05       0
Bank Sta=4990.5,4998.7
Exp/Cntr=0.3,0.1

Type RM Length L Ch R = 1,15000,500,500,500
BEGIN DESCRIPTION:
SANFERNANDO038 30.0
END DESCRIPTION:
XS GIS Cut Line= 3
      2776755.69     10258103.14      2776544.80     10257466.67
      2775555.67     10257503.11
#Sta/Elev= 30
  4329.5 1201.20  4371.7 1199.02  4377.1 1197.73  4392.7 1197.29  4408.8 1194.66
  4440.5 1192.19  4455.9 1192.70  4509.1 1186.61  4529.7 1186.18  4604.2 1181.20
  4614.0 1181.78  4635.9 1180.31  4656.1 1180.51  4677.2 1178.76  4736.7 1177.54
  4841.7 1174.66  4938.0 1172.95  4989.1 1169.11  4989.6 1168.61  4997.4 1169.11
  5019.1 1169.44  5036.6 1172.04  5076.9 1173.36  5175.9 1178.00  5209.3 1179.40
  5274.9 1179.93  5329.3 1180.91  5469.4 1180.31  5559.5 1181.07  5989.8 1190.63
#Mann=9,-1,0
  4329.5    0.05       0  4736.7    0.12       0  4841.7    0.05       0
  4938.0    0.12       0  4989.1    0.07       0  4997.4    0.12       0
  5076.9    0.05       0  5175.9    0.12       0  5274.9    0.05       0
Bank Sta=4989.1,4997.4
Exp/Cntr=0.3,0.1

Type RM Length L Ch R = 1,14500,500,500,500
BEGIN DESCRIPTION:
SANFERNANDO038 29.0
END DESCRIPTION:
XS GIS Cut Line= 3
      2776905.68     10258053.11      2776866.40     10257088.41
      2775855.69     10256253.12
#Sta/Elev= 30
  4034.5 1194.51  4274.7 1185.38  4401.5 1183.19  4414.8 1181.29  4464.9 1179.42
  4585.0 1176.20  4605.0 1177.07  4655.0 1173.21  4705.1 1171.91  4725.1 1173.90
  4765.1 1170.11  4815.1 1170.59  4845.2 1173.83  4865.2 1172.39  4935.2 1171.46
  4975.3 1167.94  4995.1 1167.40  4999.7 1165.98  5000.2 1165.48  5008.1 1165.98
  5032.6 1170.65  5107.2 1173.70  5168.1 1175.71  5230.9 1175.91  5323.9 1177.02
  5366.1 1177.71  5569.6 1175.93  5806.4 1179.32  6182.9 1190.56  6311.2 1193.19
#Mann=7,-1,0
  4034.5    0.05       0  4999.7    0.05       0  5008.1    0.05       0
  5107.2    0.12       0  5230.9    0.05       0  5323.9    0.12       0
  5569.6    0.05       0
Bank Sta=4999.7,5008.1
Exp/Cntr=0.3,0.1

Type RM Length L Ch R = 1,14000,500,500,500
BEGIN DESCRIPTION:
SANFERNANDO038 28.0
END DESCRIPTION:
XS GIS Cut Line= 3
      2776955.68     10257903.13      2777338.06     10256932.43
      2776705.67     10255553.09
#Sta/Elev= 30
  3956.7 1189.37  3996.0 1187.55  4117.9 1187.55  4150.2 1185.91  4247.7 1186.29
  4326.3 1184.71  4459.0 1178.32  4602.4 1174.59  4621.5 1172.87  4633.8 1174.00
  4666.1 1172.32  4927.4 1168.15  4969.5 1166.15  4976.1 1165.15  4981.5 1166.07
  4992.0 1163.93  4992.5 1163.43  5001.9 1163.93  5045.2 1168.13  5131.3 1170.10
  5173.6 1168.58  5263.3 1167.02  5298.4 1168.16  5340.6 1170.59  5378.2 1171.98
  5401.2 1171.33  5582.3 1174.17  6118.7 1186.93  6267.6 1188.12  6517.4 1193.45
#Mann=7,-1,0
  3956.7    0.05       0  4969.5    0.12       0  4992.0    0.07       0
  5001.9    0.12       0  5173.6    0.05       0  5298.4    0.12       0
  5340.6    0.05       0
Bank Sta=4992,5001.9
Exp/Cntr=0.3,0.1

Type RM Length L Ch R = 1,13500,500,500,500
BEGIN DESCRIPTION:
SANFERNANDO038 27.0
END DESCRIPTION:
XS GIS Cut Line= 3
      2777955.69     10258053.14      2777716.42     10256734.98
      2777005.71     10255903.15
#Sta/Elev= 30
  3660.3 1193.91  3721.3 1192.79  3915.9 1182.56  4107.5 1176.23  4251.6 1173.86
  4280.3 1171.39  4411.8 1169.19  4470.3 1171.82  4503.9 1169.62  4582.2 1169.92
  4635.6 1168.86  4640.6 1167.16  4676.7 1168.60  4717.3 1166.61  4829.1 1165.90
  4864.4 1167.62  4879.9 1165.64  4952.7 1163.46  5010.7 1160.56  5011.2 1160.06
  5020.6 1160.56  5023.2 1163.27  5088.5 1165.41  5101.2 1167.67  5129.7 1168.33
  5363.5 1169.42  5406.4 1172.96  5470.0 1174.77  5753.3 1176.98  6094.1 1186.71
#Mann=5,-1,0
  3660.3    0.05       0  4952.7    0.12       0  5010.7    0.07       0
  5020.6    0.12       0  5088.5    0.05       0
Bank Sta=5010.7,5020.6
Exp/Cntr=0.3,0.1