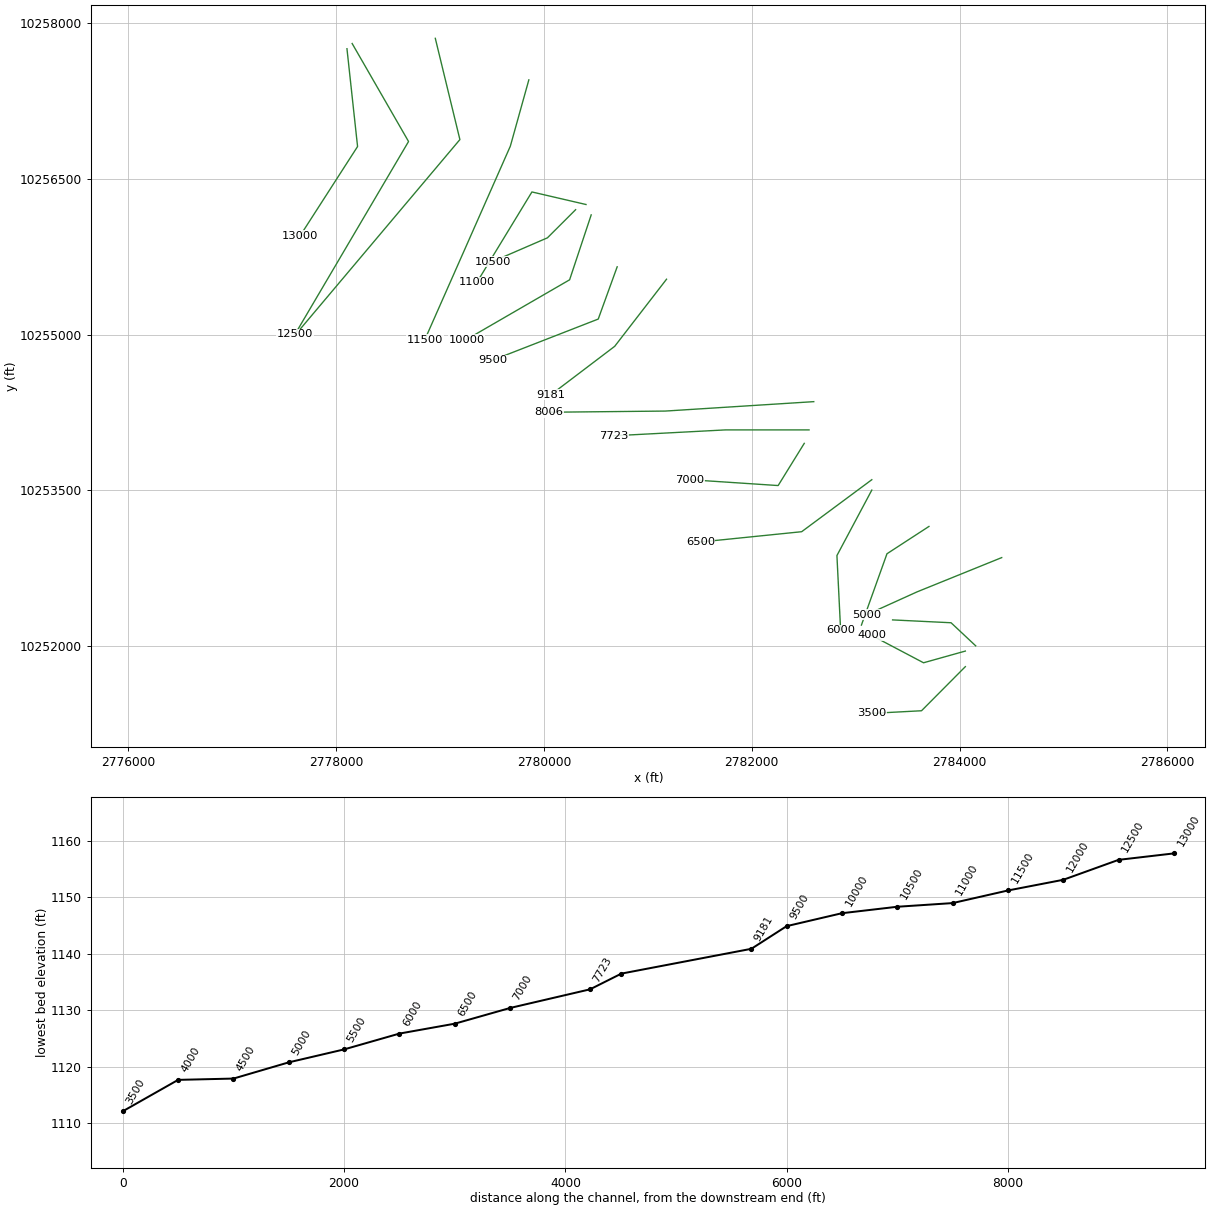
HEC-RAS study SANFERNANDO038.prj: SANFERNANDO038 Base Level Engineering

--- SANFERNANDO038.g01 (geometry) --- (continued)

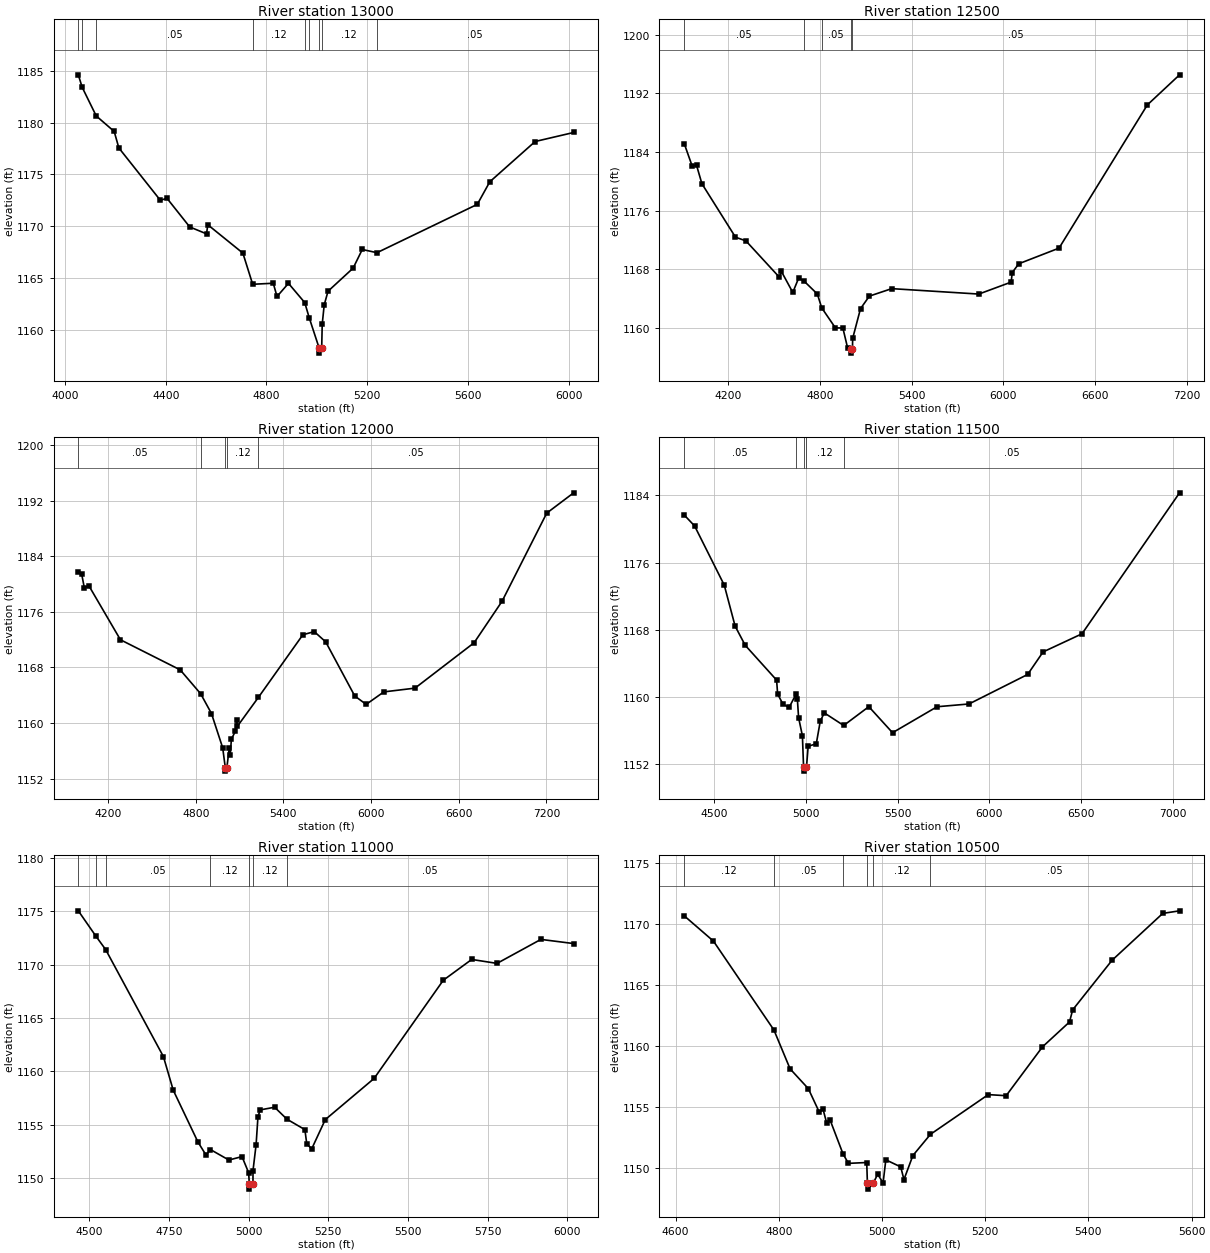
Type RM Length L Ch R = 1,13000,500,500,500
BEGIN DESCRIPTION:
SANFERNANDO038 26.0
END DESCRIPTION:
XS GIS Cut Line= 3
      2778105.68     10257753.16      2778207.72     10256811.27
      2777655.67     10255953.09
#Sta/Elev= 30
  4052.6 1184.62  4067.9 1183.42  4123.8 1180.65  4195.2 1179.15  4213.6 1177.56
  4378.6 1172.50  4404.7 1172.70  4495.2 1169.93  4562.0 1169.26  4567.0 1170.14
  4706.4 1167.40  4745.3 1164.39  4827.1 1164.49  4842.0 1163.21  4887.5 1164.48
  4952.2 1162.62  4969.9 1161.16  5009.2 1158.24  5009.7 1157.74  5019.5 1158.24
  5021.6 1160.54  5029.5 1162.40  5044.7 1163.72  5144.4 1165.95  5180.7 1167.75
  5239.1 1167.44  5637.7 1172.11  5687.4 1174.29  5867.5 1178.18  6020.4 1179.05
#Mann=9,-1,0
  4052.6    0.05       0  4067.9    0.12       0  4123.8    0.05       0
  4745.3    0.12       0  4952.2    0.05       0  4969.9    0.12       0
  5009.2    0.07       0  5019.5    0.12       0  5239.1    0.05       0
Bank Sta=5009.2,5019.5
Exp/Cntr=0.3,0.1

Type RM Length L Ch R = 1,12500,500,500,500
BEGIN DESCRIPTION:
SANFERNANDO038 25.0
END DESCRIPTION:
XS GIS Cut Line= 3
      2778155.68     10257803.12      2778698.31     10256859.74
      2777605.67     10255003.09
#Sta/Elev= 30
  3911.7 1185.16  3962.7 1182.15  3992.5 1182.19  4027.4 1179.69  4247.3 1172.40
  4315.5 1171.90  4534.7 1166.94  4547.7 1167.74  4622.4 1164.87  4659.8 1166.78
  4693.0 1166.48  4783.4 1164.65  4811.5 1162.78  4901.3 1160.04  4950.2 1160.03
  4981.8 1157.26  5002.4 1157.10  5002.9 1156.60  5013.0 1157.10  5014.3 1158.60
  5065.7 1162.66  5123.7 1164.37  5270.1 1165.39  5840.2 1164.65  6052.0 1166.28
  6058.9 1167.58  6101.8 1168.78  6365.3 1170.91  6943.4 1190.43  7154.3 1194.53
#Mann=5,-1,0
  3911.7    0.05       0  4693.0    0.12       0  4811.5    0.05       0
  5002.4    0.05       0  5013.0    0.05       0
Bank Sta=5002.4,5013
Exp/Cntr=0.3,0.1

Type RM Length L Ch R = 1,12000,500,500,500
BEGIN DESCRIPTION:
SANFERNANDO038 24.0
END DESCRIPTION:
XS GIS Cut Line= 3
      2778955.68     10257853.13      2779192.32     10256878.24
      2777655.66     10255053.08
#Sta/Elev= 30
  3996.8 1181.78  4020.3 1181.37  4038.0 1179.44  4068.9 1179.75  4285.0 1171.97
  4693.9 1167.64  4834.0 1164.20  4907.9 1161.36  4984.7 1156.42  5002.5 1153.57
  5003.0 1153.07  5013.2 1153.57  5030.0 1156.44  5036.5 1155.43  5044.2 1157.68
  5072.1 1158.82  5079.4 1160.44  5085.9 1159.54  5228.6 1163.67  5533.3 1172.69
  5611.3 1173.14  5689.4 1171.67  5888.3 1163.88  5966.4 1162.67  6087.3 1164.47
  6300.5 1165.01  6705.0 1171.54  6896.2 1177.51  7201.8 1190.19  7385.9 1193.11
#Mann=5,-1,0
  3996.8    0.05       0  4834.0    0.12       0  5002.5    0.07       0
  5013.2    0.12       0  5228.6    0.05       0
Bank Sta=5002.5,5013.2
Exp/Cntr=0.3,0.1

Type RM Length L Ch R = 1,11500,500,500,500
BEGIN DESCRIPTION:
SANFERNANDO038 23.0
END DESCRIPTION:
XS GIS Cut Line= 3
      2779855.69     10257453.12      2779677.84     10256815.15
      2778855.67     10254953.08
#Sta/Elev= 30
  4337.7 1181.65  4394.2 1180.35  4555.7 1173.31  4614.9 1168.43  4669.9 1166.15
  4840.8 1162.01  4846.4 1160.36  4875.0 1159.16  4908.7 1158.75  4946.9 1160.34
  4953.8 1159.80  4960.6 1157.54  4981.4 1155.38  4987.7 1151.68  4988.2 1151.18
  4998.7 1151.68  5003.8 1151.70  5012.7 1154.14  5056.9 1154.43  5078.7 1157.13
  5100.6 1158.11  5206.2 1156.61  5343.1 1158.85  5472.3 1155.75  5714.6 1158.84
  5888.7 1159.17  6208.1 1162.68  6292.1 1165.36  6504.2 1167.52  7035.5 1184.29
#Mann=5,-1,0
  4337.7    0.05       0  4946.9    0.12       0  4987.7    0.07       0
  4998.7    0.12       0  5206.2    0.05       0
Bank Sta=4987.7,4998.7
Exp/Cntr=0.3,0.1

Type RM Length L Ch R = 1,11000,500,500,500
BEGIN DESCRIPTION:
SANFERNANDO038 22.0
END DESCRIPTION:
XS GIS Cut Line= 3
      2780405.67     10256253.12      2779885.32     10256373.97
      2779355.67     10255503.09
#Sta/Elev= 30
  4465.8 1175.05  4521.3 1172.66  4551.5 1171.42  4732.7 1161.38  4763.5 1158.23
  4841.0 1153.37  4866.2 1152.15  4880.3 1152.66  4938.0 1151.68  4979.2 1152.00
  5000.0 1150.49  5002.1 1149.45  5002.6 1148.95  5013.6 1149.45  5013.7 1150.69
  5023.4 1153.12  5029.2 1155.72  5036.1 1156.38  5081.5 1156.63  5120.1 1155.51
  5176.4 1154.53  5182.3 1153.20  5197.7 1152.72  5240.4 1155.47  5393.5 1159.33
  5610.5 1168.54  5699.6 1170.49  5779.0 1170.12  5916.6 1172.37  6019.3 1171.98
#Mann=7,-1,0
  4465.8    0.05       0  4521.3    0.12       0  4551.5    0.05       0
  4880.3    0.12       0  5002.1    0.07       0  5013.6    0.12       0
  5120.1    0.05       0
Bank Sta=5002.1,5013.6
Exp/Cntr=0.3,0.1

Type RM Length L Ch R = 1,10500,500,500,500
BEGIN DESCRIPTION:
SANFERNANDO038 21.0
END DESCRIPTION:
XS GIS Cut Line= 3
      2780305.69     10256203.12      2780034.75     10255932.28
      2779505.65     10255703.10
#Sta/Elev= 30
  4616.9 1170.68  4673.5 1168.61  4790.7 1161.33  4822.0 1158.15  4857.3 1156.53
  4878.5 1154.61  4885.6 1154.88  4892.7 1153.75  4899.8 1153.93  4924.6 1151.18
  4935.1 1150.41  4970.5 1150.48  4971.8 1148.80  4972.3 1148.30  4983.3 1148.80
  4991.7 1149.52  5002.2 1148.81  5007.5 1150.70  5036.4 1150.12  5042.6 1149.08
  5059.9 1151.05  5094.0 1152.79  5206.0 1156.04  5240.6 1155.95  5311.0 1159.95
  5363.4 1161.99  5369.5 1162.98  5445.8 1167.04  5544.1 1170.88  5576.6 1171.09
#Mann=6,-1,0
  4616.9    0.12       0  4790.7    0.05       0  4924.6    0.12       0
  4971.8    0.07       0  4983.3    0.12       0  5094.0    0.05       0
Bank Sta=4971.8,4983.3
Exp/Cntr=0.3,0.1

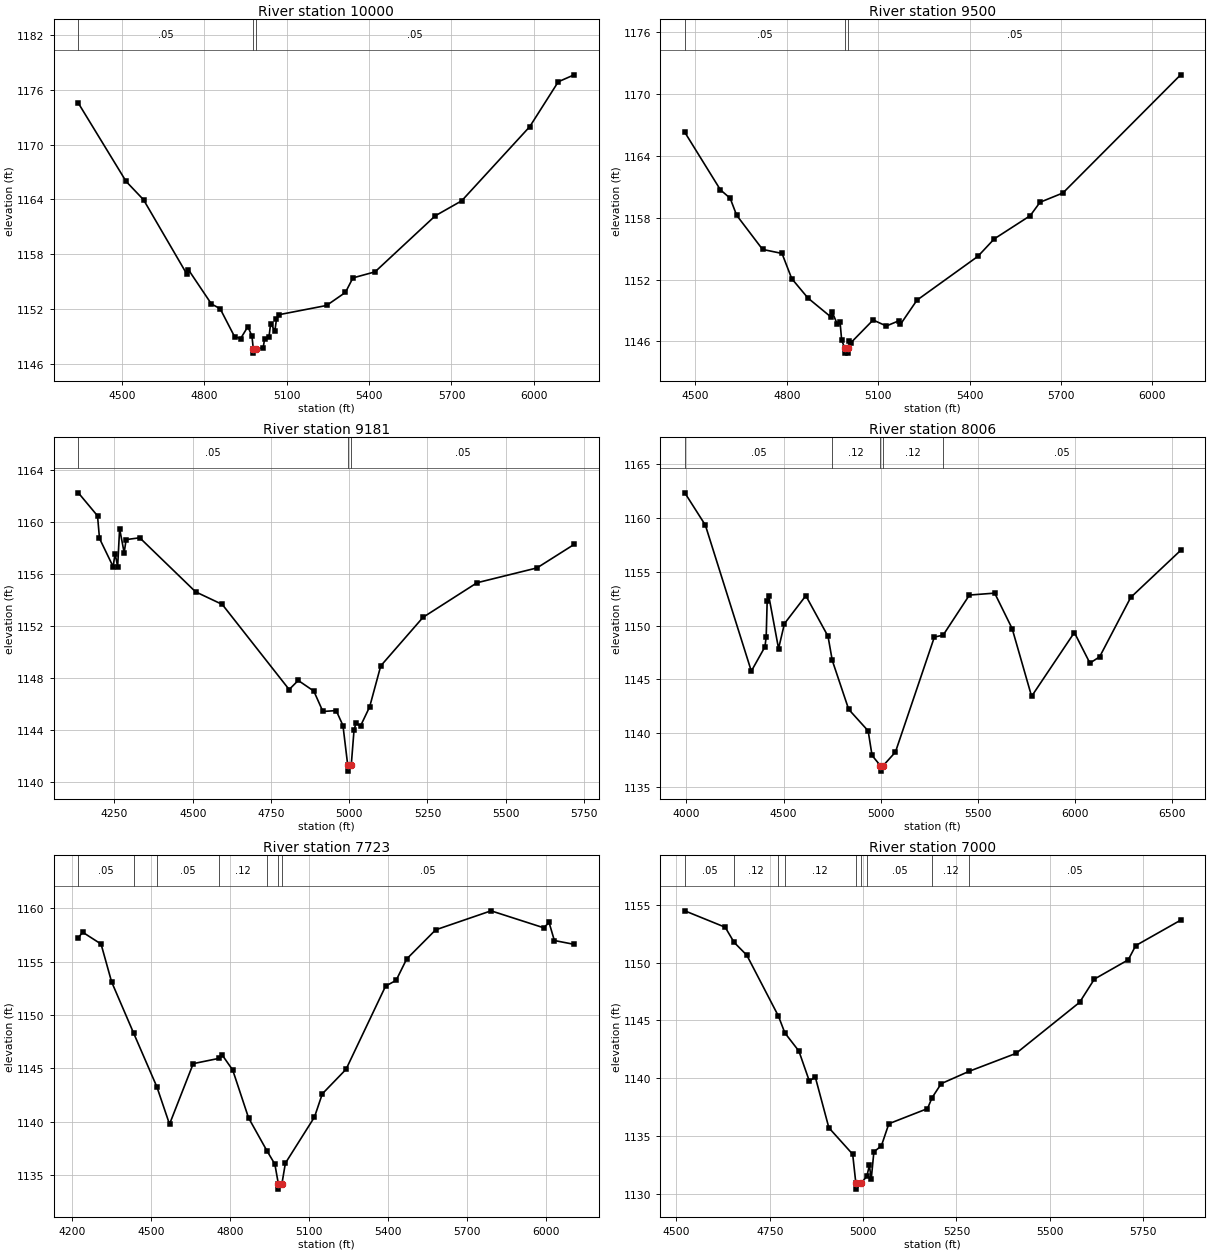
Type RM Length L Ch R = 1,10000,500,500,500
BEGIN DESCRIPTION:
SANFERNANDO038 20.0
END DESCRIPTION:
XS GIS Cut Line= 3
      2780455.68     10256153.09      2780247.96     10255528.00
      2779255.67     10254953.10
#Sta/Elev= 30
  4341.3 1174.54  4515.4 1165.96  4578.7 1163.96  4737.1 1155.78  4742.3 1156.29
  4826.0 1152.54  4857.6 1152.03  4910.3 1148.96  4932.3 1148.76  4958.7 1150.06
  4973.5 1149.02  4978.3 1147.66  4978.8 1147.16  4989.8 1147.66  5014.1 1147.70
  5019.8 1148.76  5035.6 1148.93  5041.4 1150.39  5057.1 1149.61  5062.9 1150.90
  5072.0 1151.37  5245.3 1152.38  5313.9 1153.81  5341.2 1155.40  5421.6 1156.06
  5641.1 1162.20  5737.2 1163.84  5985.0 1171.96  6089.0 1176.88  6146.8 1177.64
#Mann=3,-1,0
  4341.3    0.05       0  4978.3    0.05       0  4989.8    0.05       0
Bank Sta=4978.3,4989.8
Exp/Cntr=0.3,0.1

Type RM Length L Ch R = 1,9500,319,319,319
BEGIN DESCRIPTION:
SANFERNANDO038 19.0
END DESCRIPTION:
XS GIS Cut Line= 3
      2780705.69     10255653.14      2780523.47     10255150.02
      2779505.72     10254753.13
#Sta/Elev= 30
  4464.9 1166.27  4581.9 1160.69  4613.8 1159.88  4635.1 1158.23  4720.2 1154.92
  4784.0 1154.53  4815.9 1152.09  4869.1 1150.21  4943.5 1148.40  4949.1 1148.81
  4964.8 1147.73  4974.5 1147.89  4979.8 1146.12  4989.9 1145.37  4990.4 1144.87
  5001.0 1144.87  5001.5 1145.37  5004.1 1146.05  5009.5 1145.86  5083.0 1148.08
  5126.4 1147.50  5167.2 1148.00  5172.6 1147.65  5226.9 1150.00  5427.0 1154.25
  5480.6 1155.94  5598.7 1158.19  5630.9 1159.49  5706.0 1160.39  6092.4 1171.84
#Mann=3,-1,0
  4464.9    0.05       0  4989.9    0.05       0  5001.5    0.05       0
Bank Sta=4989.9,5001.5
Exp/Cntr=0.3,0.1

Type RM Length L Ch R = 1,9181,1175,1175,1175
BEGIN DESCRIPTION:
Mapping XS 2e207335
END DESCRIPTION:
XS GIS Cut Line= 3
      2781180.49     10255533.52      2780681.78     10254887.46
      2780070.23     10254423.14
#Sta/Elev= 30
  4134.6 1162.28  4195.9 1160.51  4202.2 1158.77  4245.7 1156.60  4252.0 1157.60
  4260.2 1156.60  4266.5 1159.52  4281.0 1157.67  4287.3 1158.68  4330.8 1158.82
  4509.2 1154.66  4594.4 1153.69  4808.1 1147.14  4837.1 1147.84  4886.9 1147.02
  4915.9 1145.45  4958.4 1145.52  4980.0 1144.37  4995.0 1141.36  4995.5 1140.86
  5006.6 1141.36  5015.4 1144.03  5021.6 1144.54  5036.2 1144.34  5065.3 1145.81
  5100.7 1148.96  5235.9 1152.70  5408.4 1155.36  5599.8 1156.50  5718.6 1158.31
#Mann=3,-1,0
  4134.6    0.05       0  4995.0    0.03       0  5006.6    0.05       0
Bank Sta=4995,5006.6
Exp/Cntr=0.3,0.1

Type RM Length L Ch R = 1,8006,283,283,283
BEGIN DESCRIPTION:
Mapping XS ccc10104
END DESCRIPTION:
XS GIS Cut Line= 3
      2782597.26     10254354.74      2781169.16     10254264.06
      2780048.89     10254252.75
#Sta/Elev= 30
  3992.0 1162.33  4097.7 1159.33  4334.3 1145.76  4404.4 1148.02  4410.8 1148.95
  4415.8 1152.24  4424.4 1152.73  4474.5 1147.85  4504.6 1150.17  4614.8 1152.77
  4728.9 1149.00  4750.8 1146.76  4835.3 1142.21  4935.5 1140.21  4955.5 1137.93
  4998.8 1136.97  4999.3 1136.47  5012.4 1136.97  5075.8 1138.24  5276.2 1148.93
  5321.1 1149.10  5456.5 1152.83  5586.5 1153.01  5676.5 1149.71  5776.5 1143.42
  5996.5 1149.35  6076.5 1146.51  6126.5 1147.09  6286.5 1152.61  6543.3 1156.98
#Mann=5,-1,0
  3992.0    0.05       0  4750.8    0.12       0  4998.8    0.07       0
  5012.4    0.12       0  5321.1    0.05       0
Bank Sta=4998.8,5012.4
Exp/Cntr=0.3,0.1

Type RM Length L Ch R = 1,7723,723,723,723
BEGIN DESCRIPTION:
Mapping XS e13fa8ef
END DESCRIPTION:
XS GIS Cut Line= 3
      2782551.96     10254082.71      2781747.22     10254082.71
      2780670.55     10254026.05
#Sta/Elev= 30
  4223.5 1157.22  4239.8 1157.75  4309.8 1156.64  4349.8 1153.10  4433.3 1148.31
  4521.9 1143.26  4569.8 1139.77  4659.8 1145.44  4756.6 1145.93  4769.8 1146.25
  4809.8 1144.84  4869.8 1140.37  4939.2 1137.30  4969.8 1136.03  4983.0 1134.19
  4983.5 1133.69  4996.6 1134.19  5009.8 1136.12  5120.3 1140.44  5149.9 1142.61
  5240.1 1144.91  5390.3 1152.70  5430.3 1153.24  5470.4 1155.24  5580.5 1157.97
  5790.8 1159.75  5991.1 1158.16  6011.1 1158.66  6031.2 1156.97  6106.4 1156.61
#Mann=7,-1,0
  4223.5    0.05       0  4433.3    0.12       0  4521.9    0.05       0
  4756.6    0.12       0  4939.2    0.05       0  4983.0    0.05       0
  4996.6    0.05       0
Bank Sta=4983,4996.6
Exp/Cntr=0.3,0.1

Type RM Length L Ch R = 1,7000,500,500,500
BEGIN DESCRIPTION:
SANFERNANDO038 14.0
END DESCRIPTION:
XS GIS Cut Line= 3
      2782505.69     10253953.12      2782254.49     10253546.80
      2781405.65     10253603.11
#Sta/Elev= 30
  4522.3 1154.48  4630.5 1153.06  4654.4 1151.75  4688.4 1150.64  4773.1 1145.37
  4790.4 1143.91  4828.0 1142.34  4856.2 1139.72  4871.6 1140.13  4908.3 1135.70
  4972.1 1133.41  4980.6 1130.89  4981.1 1130.39  4994.4 1130.89  5010.1 1131.51
  5016.8 1132.45  5021.8 1131.26  5028.9 1133.62  5048.9 1134.13  5069.0 1136.05
  5172.5 1137.36  5184.9 1138.31  5209.3 1139.52  5284.1 1140.59  5409.7 1142.14
  5580.1 1146.56  5619.6 1148.57  5710.4 1150.24  5730.4 1151.47  5850.7 1153.67
#Mann=9,-1,0
  4522.3    0.05       0  4654.4    0.12       0  4773.1    0.05       0
  4790.4    0.12       0  4980.6    0.07       0  4994.4    0.12       0
  5010.1    0.05       0  5184.9    0.12       0  5284.1    0.05       0
Bank Sta=4980.6,4994.4
Exp/Cntr=0.3,0.1

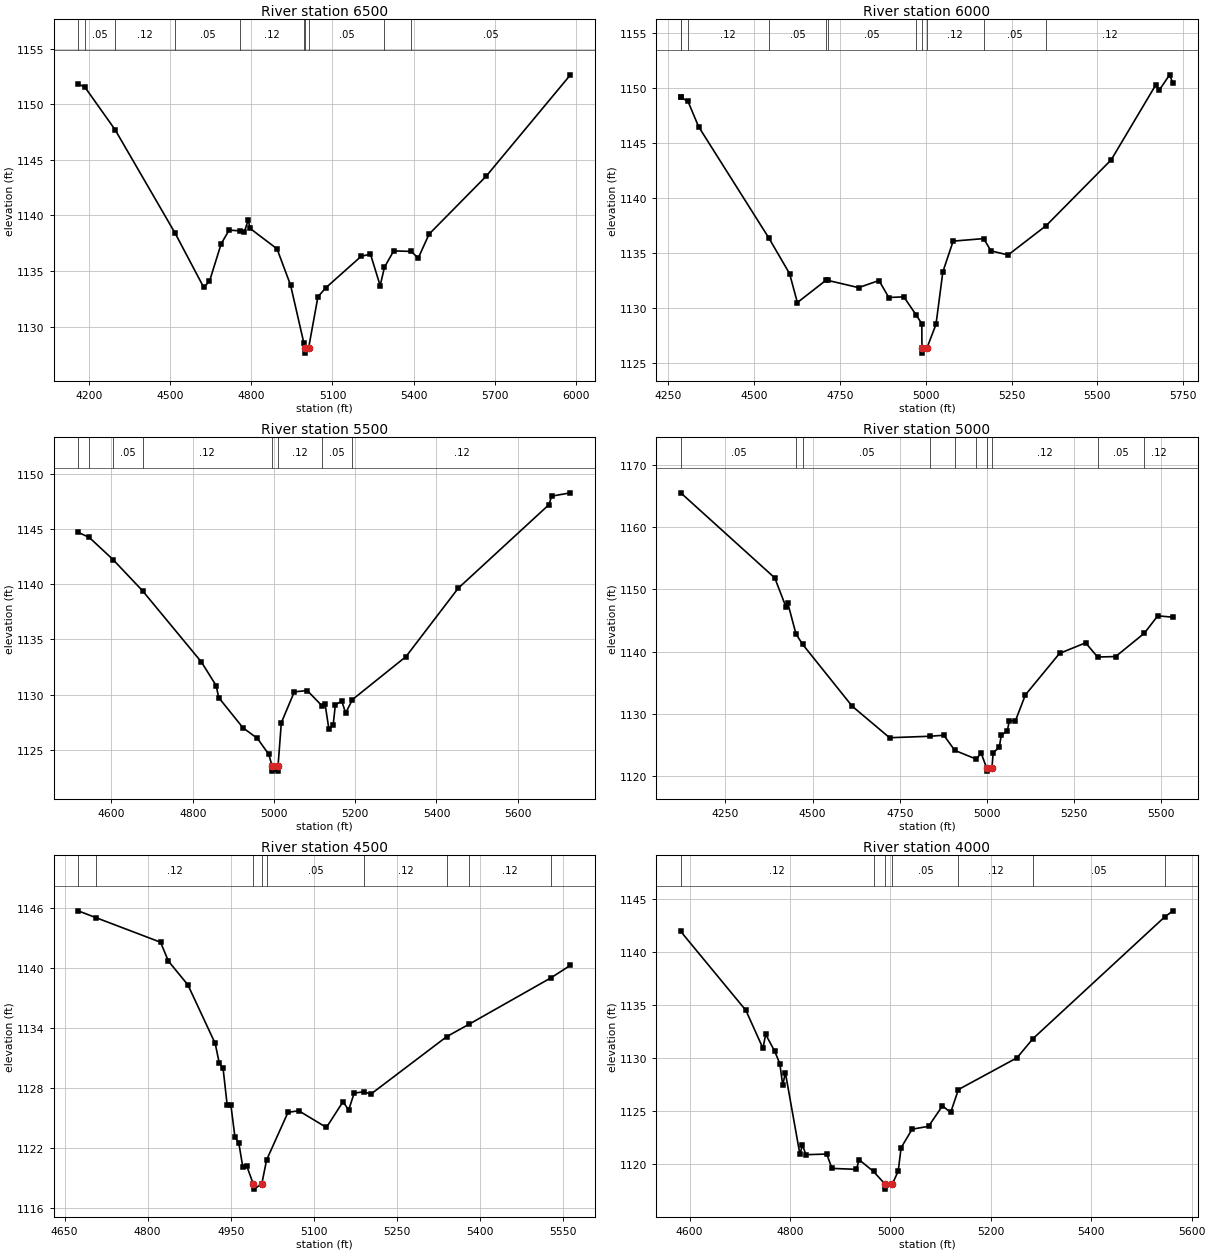
Type RM Length L Ch R = 1,6500,500,500,500
BEGIN DESCRIPTION:
SANFERNANDO038 13.0
END DESCRIPTION:
XS GIS Cut Line= 3
      2783155.69     10253603.12      2782480.75     10253102.39
      2781505.69     10253003.11
#Sta/Elev= 30
  4159.6 1151.83  4184.6 1151.54  4296.2 1147.71  4518.4 1138.39  4623.9 1133.53
  4645.2 1134.07  4688.5 1137.45  4717.8 1138.68  4756.7 1138.61  4774.1 1138.51
  4788.7 1139.61  4794.9 1138.84  4895.1 1136.99  4945.2 1133.72  4994.0 1128.54
  4998.1 1128.11  4998.6 1127.61  5012.1 1128.11  5046.3 1132.68  5075.5 1133.49
  5206.1 1136.32  5240.5 1136.52  5276.5 1133.68  5292.4 1135.35  5326.7 1136.81
  5391.2 1136.76  5417.2 1136.16  5457.4 1138.32  5668.5 1143.53  5980.1 1152.65
#Mann=10,-1,0
  4159.6    0.12       0  4184.6    0.05       0  4296.2    0.12       0
  4518.4    0.05       0  4756.7    0.12       0  4994.0    0.05       0
  4998.1    0.05       0  5012.1    0.05       0  5292.4    0.12       0
  5391.2    0.05       0
Bank Sta=4998.1,5012.1
Exp/Cntr=0.3,0.1

Type RM Length L Ch R = 1,6000,500,500,500
BEGIN DESCRIPTION:
SANFERNANDO038 12.0
END DESCRIPTION:
XS GIS Cut Line= 3
      2783155.70     10253503.13      2782820.05     10252872.83
      2782855.68     10252153.11
#Sta/Elev= 30
  4285.9 1149.17  4287.6 1149.17  4307.2 1148.80  4338.0 1146.50  4542.0 1136.39
  4603.2 1133.10  4625.8 1130.47  4709.9 1132.52  4714.7 1132.49  4804.3 1131.83
  4863.7 1132.48  4892.2 1130.93  4936.1 1130.99  4972.1 1129.33  4988.4 1128.55
  4988.9 1126.36  4989.4 1125.86  5003.8 1126.36  5029.8 1128.48  5049.8 1133.27
  5079.8 1136.07  5168.7 1136.30  5190.0 1135.18  5240.0 1134.81  5351.1 1137.49
  5540.4 1143.48  5670.5 1150.32  5680.6 1149.84  5710.6 1151.23  5720.6 1150.44
#Mann=11,-1,0
  4285.9    0.12       0  4287.6    0.05       0  4307.2    0.12       0
  4542.0    0.05       0  4709.9    0.12       0  4714.7    0.05       0
  4972.1    0.12       0  4988.9    0.07       0  5003.8    0.12       0
  5168.7    0.05       0  5351.1    0.12       0
Bank Sta=4988.9,5003.8
Exp/Cntr=0.3,0.1

Type RM Length L Ch R = 1,5500,500,500,500
BEGIN DESCRIPTION:
SANFERNANDO038 11.0
END DESCRIPTION:
XS GIS Cut Line= 3
      2783705.66     10253153.10      2783301.68     10252890.18
      2783055.68     10252203.09
#Sta/Elev= 30
  4518.0 1144.69  4545.3 1144.23  4603.6 1142.23  4676.4 1139.40  4821.3 1132.95
  4857.6 1130.81  4864.0 1129.72  4923.6 1126.99  4959.4 1126.02  4987.4 1124.57
  4995.0 1123.56  4995.5 1123.06  5009.6 1123.06  5010.1 1123.56  5018.1 1127.44
  5050.0 1130.24  5081.9 1130.36  5117.6 1129.00  5125.6 1129.18  5135.0 1126.92
  5145.6 1127.21  5151.1 1129.06  5166.8 1129.41  5176.5 1128.32  5193.1 1129.54
  5325.1 1133.44  5453.6 1139.63  5676.7 1147.19  5683.6 1147.97  5729.8 1148.27
#Mann=8,-1,0
  4518.0    0.05       0  4545.3    0.12       0  4603.6    0.05       0
  4676.4    0.12       0  4995.0    0.07       0  5010.1    0.12       0
  5117.6    0.05       0  5193.1    0.12       0
Bank Sta=4995,5010.1
Exp/Cntr=0.3,0.1

Type RM Length L Ch R = 1,5000,500,500,500
BEGIN DESCRIPTION:
SANFERNANDO038 10.0
END DESCRIPTION:
XS GIS Cut Line= 3
      2784405.64     10252853.09      2783591.71     10252523.31
      2783105.67     10252303.11
#Sta/Elev= 30
  4121.8 1165.52  4391.5 1151.84  4423.2 1147.21  4428.6 1147.83  4452.3 1142.82
  4471.3 1141.16  4613.5 1131.21  4720.8 1126.14  4837.4 1126.38  4876.2 1126.54
  4907.9 1124.10  4968.9 1122.71  4983.4 1123.65  4999.1 1121.27  4999.6 1120.77
  5014.2 1121.27  5017.8 1123.73  5035.4 1124.61  5040.9 1126.51  5058.5 1127.26
  5064.0 1128.87  5081.6 1128.86  5110.2 1133.03  5208.1 1139.70  5282.9 1141.40
  5317.2 1139.12  5368.9 1139.19  5451.4 1142.95  5489.7 1145.74  5533.6 1145.52
#Mann=10,-1,0
  4121.8    0.05       0  4452.3    0.12       0  4471.3    0.05       0
  4837.4    0.12       0  4907.9    0.05       0  4968.9    0.12       0
  4999.1    0.07       0  5014.2    0.12       0  5317.2    0.05       0
  5451.4    0.12       0
Bank Sta=4999.1,5014.2
Exp/Cntr=0.3,0.1

Type RM Length L Ch R = 1,4500,500,500,500
BEGIN DESCRIPTION:
SANFERNANDO038 9.0
END DESCRIPTION:
XS GIS Cut Line= 3
      2784155.70     10252003.10      2783918.25     10252225.73
      2783355.72     10252253.11
#Sta/Elev= 30
  4674.5 1145.74  4706.5 1145.06  4823.2 1142.60  4837.4 1140.71  4872.6 1138.33
  4921.9 1132.47  4929.2 1130.51  4936.1 1129.99  4943.4 1126.36  4950.3 1126.28
  4957.6 1123.07  4964.4 1122.55  4971.7 1120.12  4978.6 1120.25  4990.7 1118.40
  4991.2 1117.90  5005.9 1118.40  5014.7 1120.82  5053.3 1125.58  5072.7 1125.74
  5122.7 1124.07  5152.7 1126.65  5162.8 1125.81  5172.8 1127.51  5190.8 1127.64
  5202.8 1127.40  5339.7 1133.15  5380.6 1134.41  5527.8 1139.03  5563.2 1140.29
#Mann=9,-1,0
  4674.5    0.05       0  4706.5    0.12       0  4990.7    0.07       0
  5005.9    0.12       0  5014.7    0.05       0  5190.8    0.12       0
  5339.7    0.05       0  5380.6    0.12       0  5527.8    0.05       0
Bank Sta=4990.7,5005.9
Exp/Cntr=0.3,0.1

Type RM Length L Ch R = 1,4000,500,500,500
BEGIN DESCRIPTION:
SANFERNANDO038 8.0
END DESCRIPTION:
XS GIS Cut Line= 3
      2784055.70     10251953.12      2783653.50     10251840.39
      2783155.68     10252103.11
#Sta/Elev= 30
  4582.3 1141.92  4712.1 1134.49  4746.2 1130.91  4751.4 1132.24  4769.3 1130.66
  4779.6 1129.49  4785.5 1127.45  4790.7 1128.63  4819.6 1120.97  4824.8 1121.82
  4831.6 1120.91  4873.1 1120.97  4883.5 1119.62  4932.3 1119.53  4937.5 1120.44
  4966.3 1119.33  4988.7 1118.17  4989.2 1117.67  5003.9 1118.17  5015.5 1119.36
  5021.2 1121.56  5043.2 1123.31  5075.9 1123.58  5103.6 1125.50  5120.0 1124.89
  5135.4 1127.04  5252.1 1130.03  5284.1 1131.84  5546.1 1143.28  5562.9 1143.86
#Mann=7,-1,0
  4582.3    0.12       0  4966.3    0.05       0  4988.7    0.05       0
  5003.9    0.05       0  5135.4    0.12       0  5284.1    0.05       0
  5546.1    0.12       0
Bank Sta=4988.7,5003.9
Exp/Cntr=0.3,0.1

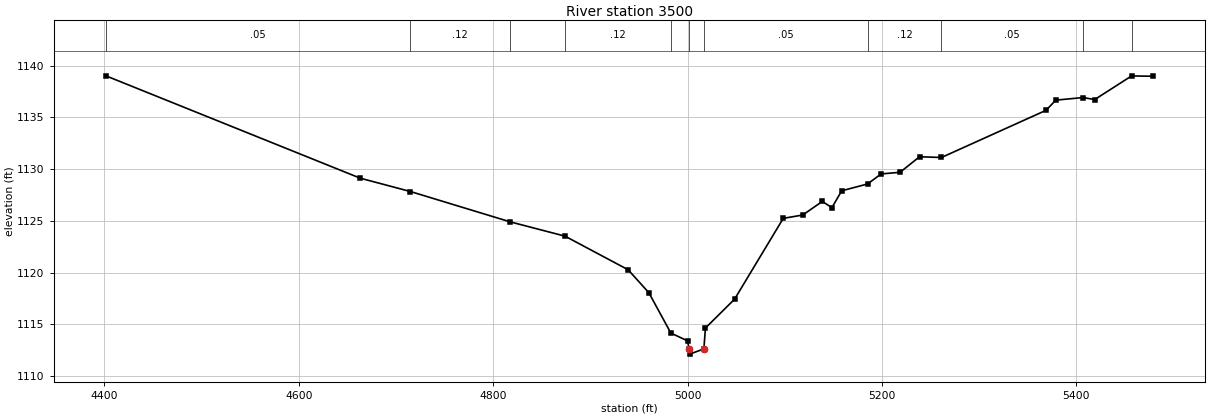
Type RM Length L Ch R = 1,3500,500,500,500
BEGIN DESCRIPTION:
SANFERNANDO038 7.0
END DESCRIPTION:
XS GIS Cut Line= 3
      2784055.71     10251803.13      2783634.06     10251378.38
      2783155.72     10251353.11
#Sta/Elev= 30
  4401.5 1139.01  4663.2 1129.12  4714.9 1127.83  4817.5 1124.90  4873.9 1123.52
  4938.9 1120.27  4960.2 1118.05  4982.8 1114.16  5000.0 1113.40  5001.6 1112.62
  5002.1 1112.12  5016.8 1112.62  5018.4 1114.64  5048.4 1117.43  5098.5 1125.24
  5118.5 1125.56  5138.6 1126.87  5148.6 1126.28  5158.6 1127.90  5185.2 1128.56
  5199.2 1129.53  5218.7 1129.69  5238.7 1131.19  5261.3 1131.12  5368.9 1135.68
  5378.9 1136.66  5406.8 1136.91  5419.0 1136.72  5456.9 1139.00  5479.0 1138.97
#Mann=11,-1,0
  4401.5    0.05       0  4714.9    0.12       0  4817.5    0.05       0
  4873.9    0.12       0  4982.8    0.05       0  5001.6    0.05       0
  5016.8    0.05       0  5185.2    0.12       0  5261.3    0.05       0
  5406.8    0.12       0  5456.9    0.05       0
Bank Sta=5001.6,5016.8
Exp/Cntr=0.3,0.1