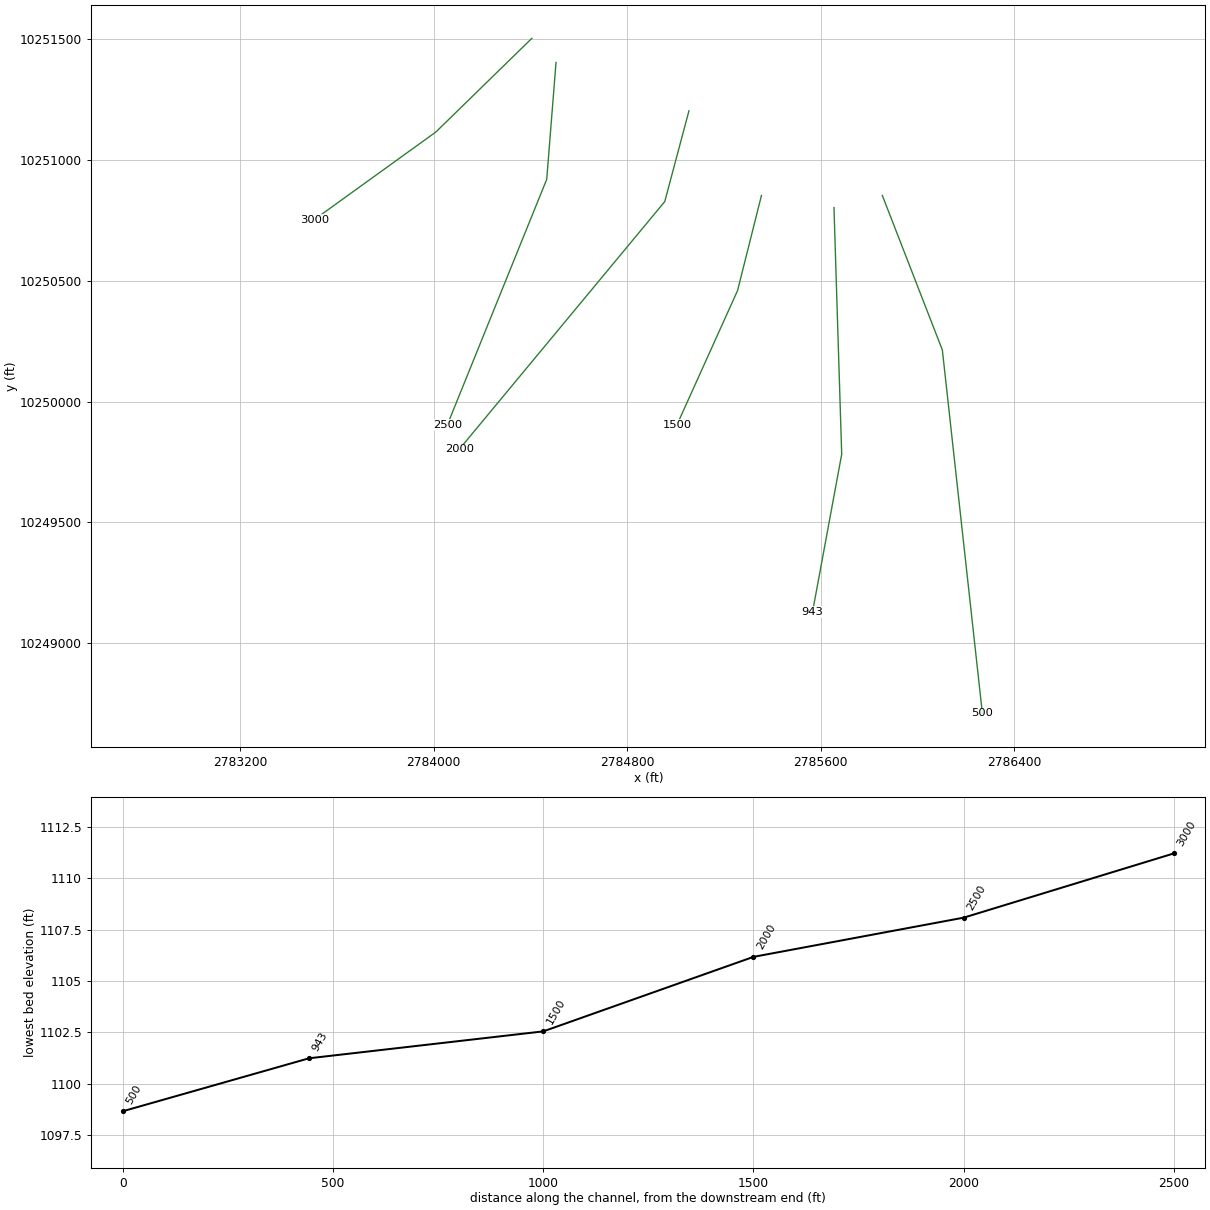
HEC-RAS study SANFERNANDO038.prj: SANFERNANDO038 Base Level Engineering

--- SANFERNANDO038.g01 (geometry) --- (continued)

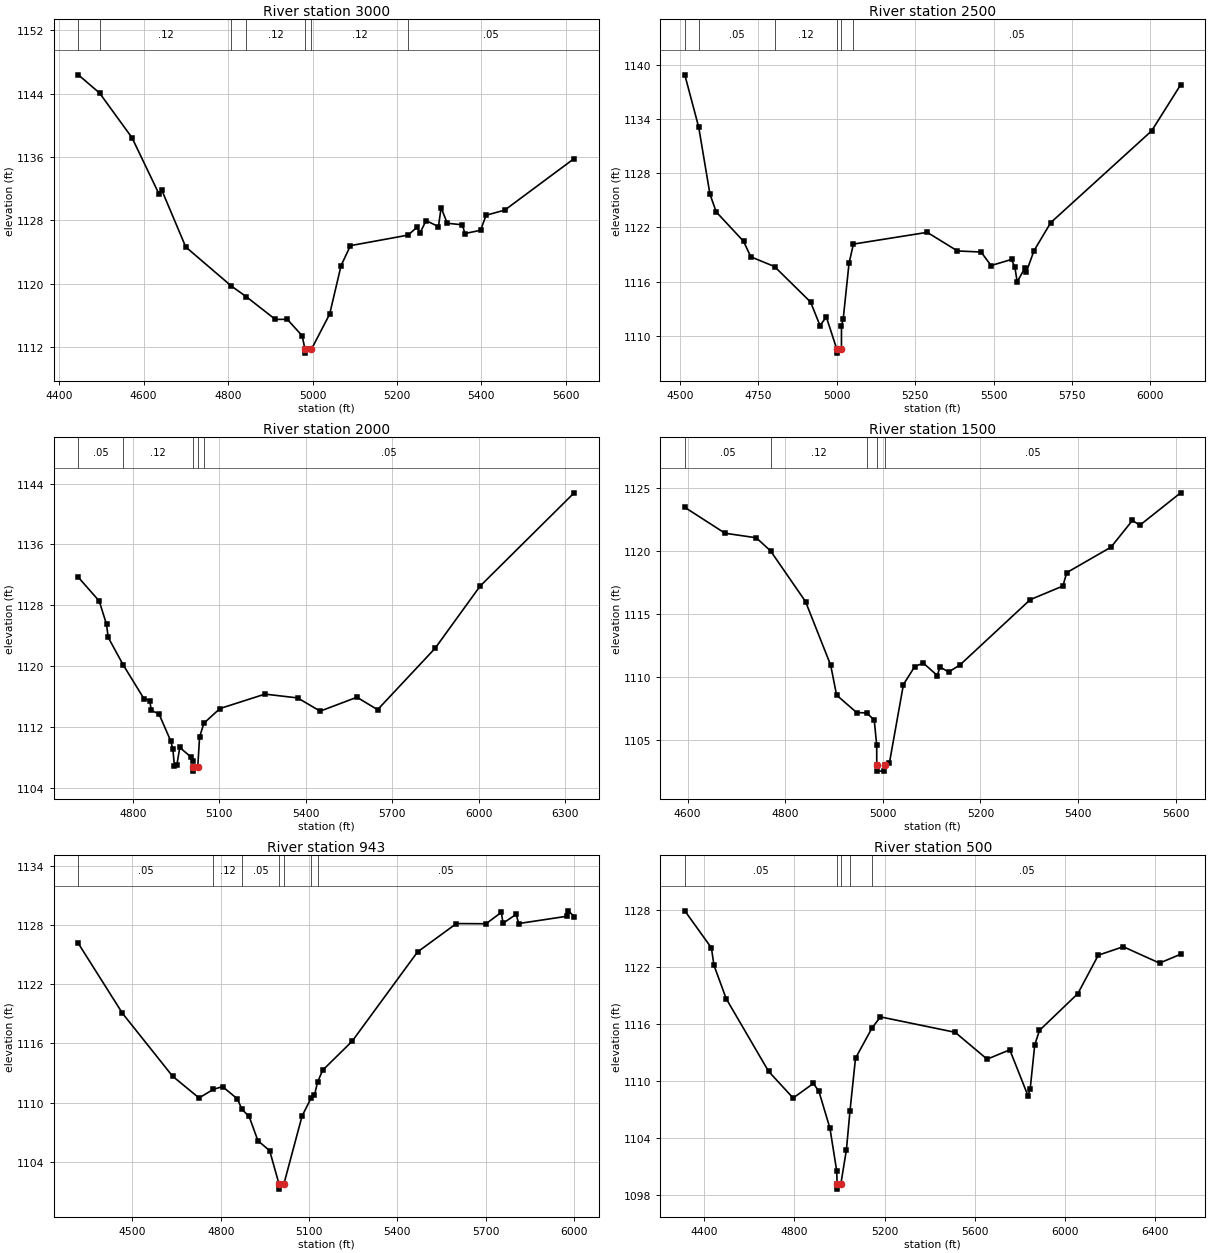
Type RM Length L Ch R = 1,3000,500,500,500
BEGIN DESCRIPTION:
SANFERNANDO038 6.0
END DESCRIPTION:
XS GIS Cut Line= 3
      2784405.66     10251503.08      2784008.63     10251115.56
      2783505.72     10250753.13
#Sta/Elev= 30
  4445.2 1146.37  4495.5 1144.07  4572.4 1138.42  4636.1 1131.34  4643.1 1131.78
  4699.7 1124.62  4807.9 1119.68  4843.1 1118.34  4911.9 1115.47  4940.2 1115.48
  4975.6 1113.40  4982.1 1111.71  4982.6 1111.21  4997.5 1111.71  5040.6 1116.13
  5067.7 1122.27  5089.9 1124.79  5226.4 1126.12  5248.1 1127.14  5254.3 1126.33
  5269.0 1127.96  5298.4 1127.19  5304.6 1129.58  5319.3 1127.62  5354.9 1127.42
  5361.1 1126.32  5398.1 1126.73  5411.3 1128.63  5455.5 1129.28  5619.9 1135.79
#Mann=7,-1,0
  4445.2    0.05       0  4495.5    0.12       0  4807.9    0.05       0
  4843.1    0.12       0  4982.1    0.07       0  4997.5    0.12       0
  5226.4    0.05       0
Bank Sta=4982.1,4997.5
Exp/Cntr=0.3,0.1

Type RM Length L Ch R = 1,2500,500,500,500
BEGIN DESCRIPTION:
SANFERNANDO038 5.0
END DESCRIPTION:
XS GIS Cut Line= 3
      2784505.68     10251403.07      2784467.23     10250919.80
      2784055.69     10249903.13
#Sta/Elev= 30
  4515.2 1138.91  4559.7 1133.09  4595.4 1125.69  4615.5 1123.72  4702.5 1120.47
  4725.8 1118.75  4801.4 1117.67  4916.4 1113.74  4946.5 1111.13  4966.6 1112.09
  4999.5 1108.58  5000.0 1108.08  5014.9 1108.58  5015.0 1111.14  5020.4 1111.84
  5039.1 1118.04  5053.0 1120.16  5288.5 1121.46  5384.8 1119.40  5460.3 1119.28
  5492.2 1117.78  5557.4 1118.46  5568.2 1117.58  5575.4 1115.98  5599.5 1117.47
  5604.9 1117.09  5629.0 1119.42  5682.6 1122.54  6004.3 1132.70  6096.8 1137.80
#Mann=6,-1,0
  4515.2    0.12       0  4559.7    0.05       0  4801.4    0.12       0
  4999.5    0.07       0  5014.9    0.12       0  5053.0    0.05       0
Bank Sta=4999.5,5014.9
Exp/Cntr=0.3,0.1

Type RM Length L Ch R = 1,2000,500,500,500
BEGIN DESCRIPTION:
SANFERNANDO038 4.0
END DESCRIPTION:
XS GIS Cut Line= 3
      2785055.70     10251203.16      2784955.56     10250827.68
      2784105.67     10249803.09
#Sta/Elev= 30
  4611.4 1131.67  4683.9 1128.54  4709.1 1125.49  4714.9 1123.77  4766.6 1120.17
  4839.1 1115.69  4859.2 1115.46  4864.3 1114.15  4890.9 1113.71  4932.3 1110.10
  4939.4 1109.02  4944.6 1106.89  4953.0 1106.95  4963.3 1109.28  5003.8 1107.97
  5010.0 1107.52  5010.1 1106.67  5010.6 1106.17  5025.6 1106.67  5031.9 1110.64
  5046.8 1112.47  5102.5 1114.40  5258.8 1116.30  5372.1 1115.80  5450.2 1114.06
  5577.8 1115.89  5649.4 1114.25  5848.7 1122.32  6005.0 1130.51  6331.2 1142.78
#Mann=5,-1,0
  4611.4    0.05       0  4766.6    0.12       0  5010.1    0.07       0
  5025.6    0.12       0  5046.8    0.05       0
Bank Sta=5010.1,5025.6
Exp/Cntr=0.3,0.1

Type RM Length L Ch R = 1,1500,557,557,557
BEGIN DESCRIPTION:
SANFERNANDO038 3.0
END DESCRIPTION:
XS GIS Cut Line= 3
      2785355.67     10250853.06      2785256.75     10250459.40
      2785005.69     10249903.13
#Sta/Elev= 30
  4594.1 1123.43  4676.5 1121.38  4740.6 1121.02  4769.9 1119.98  4841.5 1115.97
  4893.1 1110.93  4905.2 1108.56  4946.3 1107.18  4966.5 1107.15  4982.3 1106.60
  4987.4 1104.60  4987.5 1103.04  4988.0 1102.54  5003.1 1102.54  5003.6 1103.04
  5013.6 1103.22  5042.2 1109.40  5065.3 1110.82  5082.9 1111.10  5111.6 1110.11
  5117.0 1110.79  5134.7 1110.39  5157.8 1110.94  5302.1 1116.12  5369.0 1117.20
  5376.9 1118.26  5467.7 1120.28  5511.6 1122.40  5526.6 1122.01  5610.3 1124.58
#Mann=5,-1,0
  4594.1    0.05       0  4769.9    0.12       0  4966.5    0.05       0
  4987.5    0.03       0  5003.6    0.05       0
Bank Sta=4987.5,5003.6
Exp/Cntr=0.3,0.1

Type RM Length L Ch R = 1,943,443,443,443
BEGIN DESCRIPTION:
SANFERNANDO038 2.0
END DESCRIPTION:
XS GIS Cut Line= 3
      2785655.68     10250803.10      2785687.63     10249782.25
      2785566.94     10249129.57
#Sta/Elev= 30
  4316.1 1126.13  4466.2 1119.04  4636.2 1112.68  4726.3 1110.47  4774.4 1111.33
  4806.3 1111.62  4856.4 1110.38  4872.6 1109.30  4896.4 1108.60  4926.4 1106.14
  4966.4 1105.12  4998.3 1101.73  4998.8 1101.23  5014.5 1101.73  5076.5 1108.64
  5107.1 1110.45  5118.5 1110.73  5129.0 1112.06  5146.5 1113.28  5246.5 1116.21
  5468.8 1125.26  5601.0 1128.14  5701.6 1128.12  5753.5 1129.27  5759.6 1128.18
  5804.4 1129.08  5812.5 1128.14  5976.4 1128.88  5981.5 1129.43  6001.2 1128.84
#Mann=7,-1,0
  4316.1    0.05       0  4774.4    0.12       0  4872.6    0.05       0
  4998.3    0.05       0  5014.5    0.05       0  5107.1    0.12       0
  5129.0    0.05       0
Bank Sta=4998.3,5014.5
Exp/Cntr=0.3,0.1

Type RM Length L Ch R = 1,500,0,0,0
BEGIN DESCRIPTION:
SANFERNANDO038 1.0
END DESCRIPTION:
XS GIS Cut Line= 3
      2785855.70     10250853.08      2786104.09     10250213.52
      2786269.67     10248710.21
#Sta/Elev= 30
  4313.9 1127.88  4431.9 1123.99  4443.1 1122.17  4497.5 1118.65  4685.4 1111.02
  4794.2 1108.22  4884.0 1109.75  4908.5 1108.92  4957.5 1105.04  4987.5 1100.56
  4989.4 1099.15  4989.9 1098.65  5005.6 1099.15  5030.6 1102.80  5046.4 1106.88
  5070.8 1112.40  5144.8 1115.60  5181.5 1116.74  5512.7 1115.12  5654.3 1112.30
  5754.9 1113.28  5835.4 1108.47  5845.5 1109.20  5865.6 1113.80  5886.5 1115.32
  6056.8 1119.19  6147.3 1123.22  6258.0 1124.11  6418.9 1122.39  6512.4 1123.32
#Mann=5,-1,0
  4313.9    0.05       0  4989.4    0.05       0  5005.6    0.05       0
  5046.4    0.12       0  5144.8    0.05       0
Bank Sta=4989.4,5005.6
Exp/Cntr=0.3,0.1

Chan Stop Cuts=-1