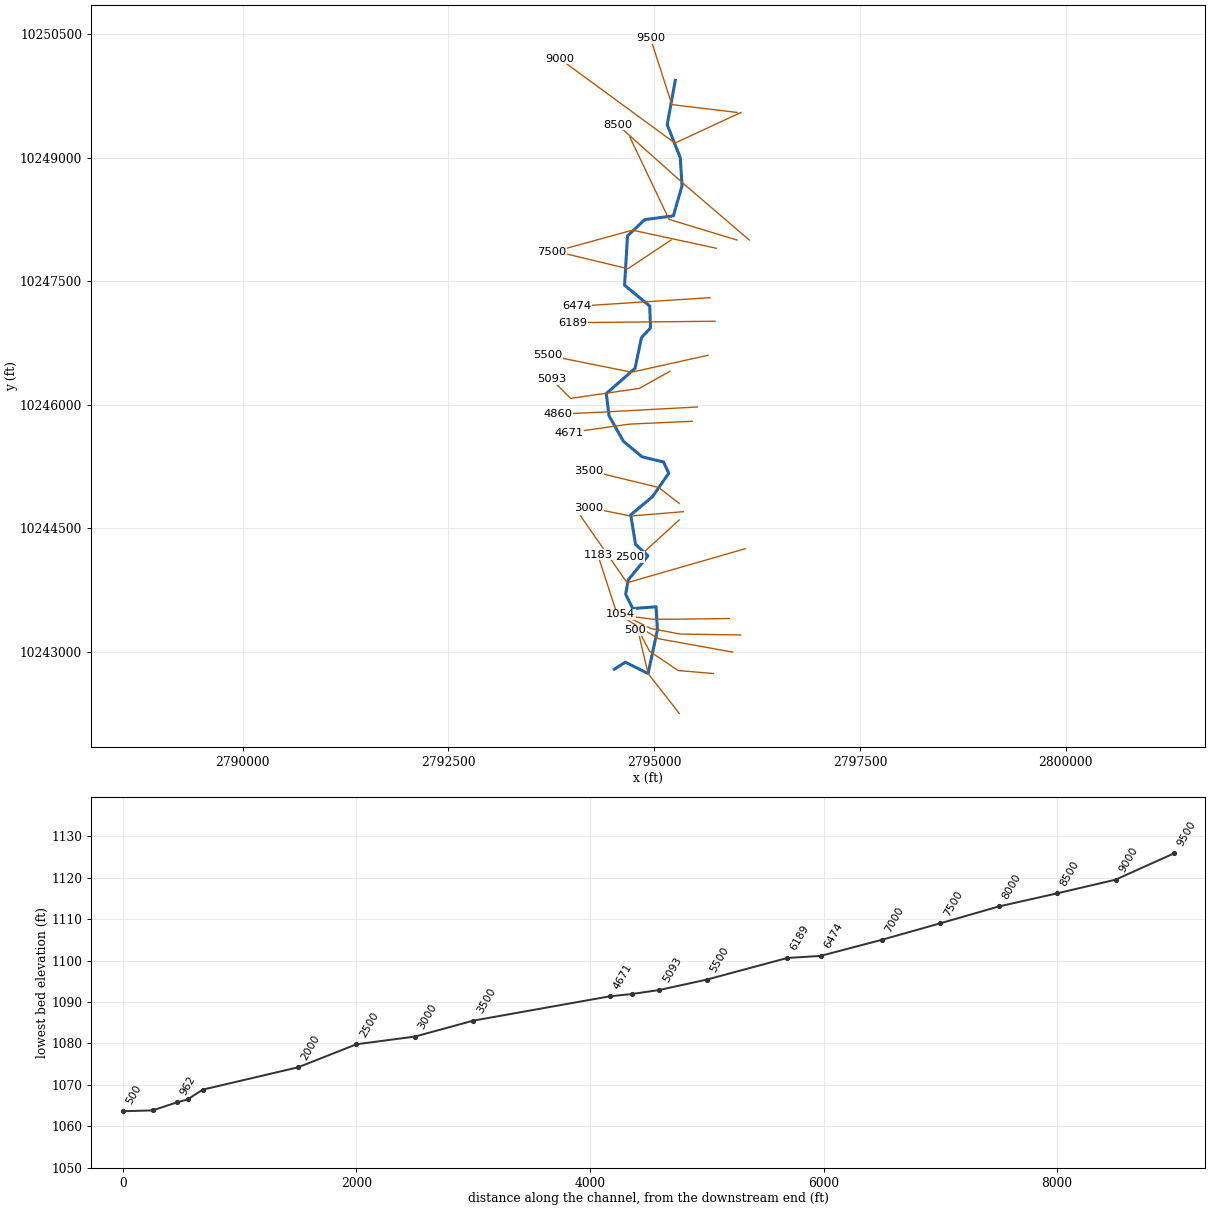
--- SANFERNANDO039.prj (project) ---

Proj Title=SANFERNANDO039 Base Level Engineering
Current Plan=p01
Default Exp/Contr=0.3,0.1
English Units
Geom File=g01
Flow File=f01
Plan File=p01
BEGIN DESCRIPTION:
SANFERNANDO039
END DESCRIPTION:

--- SANFERNANDO039.p01 (plan) ---

Plan Title=Multiple Run
Short Identifier=Multiple
Geom File=g01
Flow File=f01
Subcritical Flow
K Sum by GR= 0
Std Step Tol= 0.01
Critical Tol= 0.01
Num of Std Step Trials= 20
Max Error Tol= 0.3
Flow Tol Ratio= 0.001
Split Flow NTrial= 30
Split Flow Tol= 0.02
Split Flow Ratio= 0.02
Log Output Level= 0
Friction Slope Method= 1
Unsteady Friction Slope Method= 2
Unsteady Bridges Friction Slope Method= 1
Parabolic Critical Depth
Global Vel Dist=  1 , 1 , 1
Global Log Level= 0
CheckData=True
Encroach Param= -1, 0, 0, 0
BEGIN DESCRIPTION:
Multiple Run
END DESCRIPTION:

--- SANFERNANDO039.f01 (steady flow) ---

Flow Title=Multiple
Number of Profiles=7
Profile Names=10-year,25-year,50-year,1pct_min,100-year,1pct_plu,500-year
River Rch & RM= SANFERNANDO039,Reach-1,9500
     452     735     770     486     998    2051    1333
Boundary for River Rch & Prof#=SANFERNANDO039,Reach-1,1
Up Type=0
Dn Type=3
Dn Slope=0.005
Boundary for River Rch & Prof#=SANFERNANDO039,Reach-1,2
Up Type=0
Dn Type=3
Dn Slope=0.005
Boundary for River Rch & Prof#=SANFERNANDO039,Reach-1,3
Up Type=0
Dn Type=3
Dn Slope=0.005
Boundary for River Rch & Prof#=SANFERNANDO039,Reach-1,4
Up Type=0
Dn Type=3
Dn Slope=0.005
Boundary for River Rch & Prof#=SANFERNANDO039,Reach-1,5
Up Type=0
Dn Type=3
Dn Slope=0.005
Boundary for River Rch & Prof#=SANFERNANDO039,Reach-1,6
Up Type=0
Dn Type=3
Dn Slope=0.005
Boundary for River Rch & Prof#=SANFERNANDO039,Reach-1,7
Up Type=0
Dn Type=3
Dn Slope=0.005

--- SANFERNANDO039.g01 (geometry) ---

Geom Title=Existing Conditions

River Reach=SANFERNANDO039,Reach-1
Reach XY= 30
      2795257.00     10249942.00      2795159.00     10249404.00
      2795317.25     10249004.00      2795339.25     10248664.00
      2795234.00     10248297.00      2794886.00     10248251.00
      2794676.25     10248053.00      2794641.25     10247454.00
      2794946.75     10247201.00      2794955.50     10246935.00
      2794846.00     10246817.00      2794768.00     10246444.00
      2794419.00     10246138.00      2794452.00     10245869.00
      2794625.75     10245560.00      2794854.75     10245369.00
      2795113.50     10245307.00      2795177.75     10245171.00
      2794979.75     10244885.00      2794716.00     10244665.00
      2794774.00     10244307.00      2794925.25     10244167.00
      2794685.50     10243875.00      2794654.25     10243701.00
      2794741.00     10243526.00      2795024.00     10243548.00
      2795039.75     10243267.00      2794926.75     10242737.00
      2794650.75     10242875.00      2794517.25     10242790.00

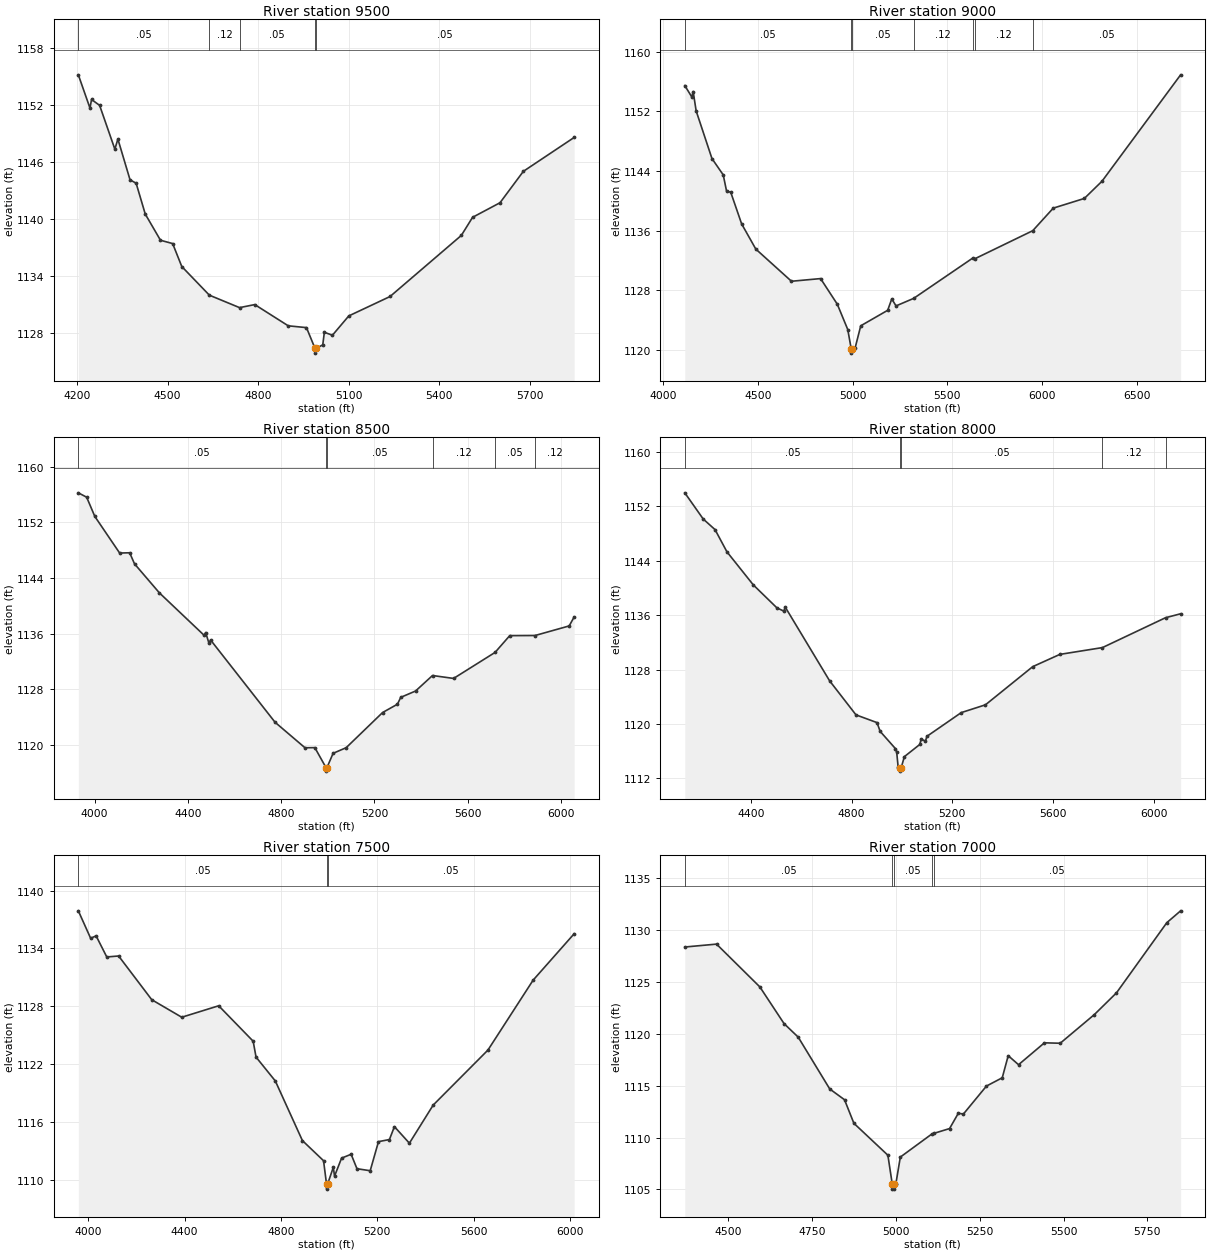
Type RM Length L Ch R = 1,9500,500,500,500
BEGIN DESCRIPTION:
SANFERNANDO039 19.0
END DESCRIPTION:
XS GIS Cut Line= 3
      2796005.71     10249553.11      2795215.88     10249647.93
      2794955.68     10250453.13
#Sta/Elev= 30
  4204.5 1155.13  4243.1 1151.63  4248.2 1152.54  4275.0 1151.92  4325.4 1147.32
  4335.5 1148.38  4375.7 1144.10  4395.9 1143.74  4426.1 1140.50  4476.5 1137.75
  4516.8 1137.40  4547.0 1134.99  4638.3 1131.98  4738.3 1130.67  4788.7 1130.99
  4899.5 1128.76  4959.9 1128.57  4988.1 1126.39  4988.4 1125.89  4992.1 1126.39
  5013.8 1126.76  5019.1 1128.08  5045.8 1127.77  5100.0 1129.80  5236.7 1131.84
  5472.7 1138.26  5509.9 1140.16  5600.7 1141.69  5678.0 1144.99  5846.2 1148.55
#Mann=5,-1,0
  4204.5    0.05       0  4638.3    0.12       0  4738.3    0.05       0
  4988.1    0.05       0  4992.1    0.05       0
Bank Sta=4988.1,4992.1
Exp/Cntr=0.3,0.1

Type RM Length L Ch R = 1,9000,500,500,500
BEGIN DESCRIPTION:
SANFERNANDO039 18.0
END DESCRIPTION:
XS GIS Cut Line= 3
      2796055.67     10249553.10      2795252.78     10249180.33
      2793855.66     10250203.13
#Sta/Elev= 30
  4114.8 1155.47  4151.9 1153.93  4158.9 1154.67  4174.8 1152.06  4258.1 1145.67
  4317.7 1143.47  4335.1 1141.31  4357.3 1141.14  4414.8 1136.89  4489.6 1133.51
  4677.7 1129.19  4831.4 1129.55  4919.6 1126.11  4974.8 1122.71  4993.6 1120.04
  4993.9 1119.54  4997.6 1120.04  5014.1 1120.28  5043.4 1123.21  5185.5 1125.29
  5207.1 1126.82  5229.5 1125.88  5322.5 1126.89  5634.8 1132.31  5647.8 1132.24
  5951.1 1135.98  6059.4 1139.01  6223.3 1140.31  6316.5 1142.62  6731.5 1156.91
#Mann=7,-1,0
  4114.8    0.05       0  4993.6    0.05       0  4997.6    0.05       0
  5322.5    0.12       0  5634.8    0.05       0  5647.8    0.12       0
  5951.1    0.05       0
Bank Sta=4993.6,4997.6
Exp/Cntr=0.3,0.1

Type RM Length L Ch R = 1,8500,500,500,500
BEGIN DESCRIPTION:
SANFERNANDO039 17.0
END DESCRIPTION:
XS GIS Cut Line= 3
      2796155.68     10248003.12      2795343.55     10248699.17
      2794555.71     10249403.09
#Sta/Elev= 30
  3930.4 1156.26  3966.1 1155.63  4001.2 1152.86  4107.6 1147.60  4150.5 1147.64
  4171.3 1146.05  4277.8 1141.88  4469.8 1135.77  4476.4 1136.17  4490.7 1134.61
  4497.3 1135.11  4773.9 1123.27  4902.3 1119.60  4944.5 1119.62  4992.5 1116.74
  4992.7 1116.24  4996.5 1116.74  5022.8 1118.80  5078.9 1119.61  5235.2 1124.67
  5298.7 1125.86  5312.9 1126.85  5376.5 1127.76  5449.1 1129.99  5539.5 1129.57
  5717.3 1133.31  5780.2 1135.72  5888.6 1135.74  6035.2 1137.12  6056.5 1138.41
#Mann=6,-1,0
  3930.4    0.05       0  4992.5    0.05       0  4996.5    0.05       0
  5449.1    0.12       0  5717.3    0.05       0  5888.6    0.12       0
Bank Sta=4992.5,4996.5
Exp/Cntr=0.3,0.1

Type RM Length L Ch R = 1,8000,500,500,500
BEGIN DESCRIPTION:
SANFERNANDO039 16.0
END DESCRIPTION:
XS GIS Cut Line= 3
      2796005.66     10248003.12      2795181.19     10248254.35
      2794705.67     10249253.13
#Sta/Elev= 30
  4138.1 1153.98  4211.2 1150.13  4258.2 1148.57  4305.3 1145.31  4409.9 1140.45
  4504.0 1137.06  4531.3 1136.59  4536.6 1137.19  4713.0 1126.34  4817.6 1121.34
  4901.2 1120.20  4913.4 1118.92  4973.9 1116.39  4979.1 1115.88  4984.8 1113.73
  4993.0 1113.57  4993.3 1113.07  4997.0 1113.57  5009.7 1115.20  5070.8 1116.99
  5076.3 1117.77  5093.5 1117.48  5099.0 1118.18  5235.3 1121.67  5331.6 1122.82
  5519.2 1128.43  5626.8 1130.23  5795.9 1131.23  6046.2 1135.62  6106.2 1136.20
#Mann=5,-1,0
  4138.1    0.05       0  4993.0    0.05       0  4997.0    0.05       0
  5795.9    0.12       0  6046.2    0.05       0
Bank Sta=4993,4997
Exp/Cntr=0.3,0.1

Type RM Length L Ch R = 1,7500,500,500,500
BEGIN DESCRIPTION:
SANFERNANDO039 15.0
END DESCRIPTION:
XS GIS Cut Line= 3
      2795755.66     10247903.12      2794737.39     10248122.80
      2793755.66     10247853.10
#Sta/Elev= 30
  3958.3 1137.91  4009.4 1135.06  4032.2 1135.31  4076.4 1133.12  4125.7 1133.22
  4263.3 1128.68  4387.9 1126.86  4541.4 1128.05  4684.6 1124.37  4696.6 1122.72
  4776.7 1120.24  4889.2 1114.05  4977.0 1111.96  4989.5 1109.51  4989.8 1109.01
  4993.5 1109.51  5017.5 1111.27  5022.7 1110.36  5051.9 1112.23  5091.6 1112.63
  5115.8 1111.13  5170.8 1110.92  5205.2 1113.94  5250.7 1114.16  5271.4 1115.50
  5333.6 1113.78  5432.5 1117.74  5659.9 1123.45  5847.6 1130.71  6018.1 1135.53
#Mann=3,-1,0
  3958.3    0.05       0  4989.5    0.03       0  4993.5    0.05       0
Bank Sta=4989.5,4993.5
Exp/Cntr=0.3,0.1

Type RM Length L Ch R = 1,7000,526,526,526
BEGIN DESCRIPTION:
SANFERNANDO039 14.0
END DESCRIPTION:
XS GIS Cut Line= 3
      2795205.65     10248003.09      2794681.36     10247654.50
      2793855.72     10247853.10
#Sta/Elev= 30
  4370.4 1128.38  4465.1 1128.66  4594.3 1124.53  4666.5 1120.99  4708.6 1119.69
  4802.7 1114.69  4846.8 1113.65  4874.7 1111.38  4976.1 1108.30  4989.1 1105.53
  4989.4 1105.03  4992.9 1105.03  4993.1 1105.53  5000.0 1105.56  5013.2 1108.12
  5107.8 1110.36  5112.5 1110.40  5160.1 1110.87  5186.2 1112.35  5201.3 1112.27
  5270.1 1114.97  5317.2 1115.77  5335.0 1117.90  5365.8 1117.03  5443.0 1119.14
  5490.1 1119.10  5592.1 1121.87  5657.9 1123.96  5808.1 1130.73  5849.2 1131.87
#Mann=5,-1,0
  4370.4    0.05       0  4989.1    0.05       0  4993.1    0.05       0
  5107.8    0.12       0  5112.5    0.05       0
Bank Sta=4989.1,4993.1
Exp/Cntr=0.3,0.1

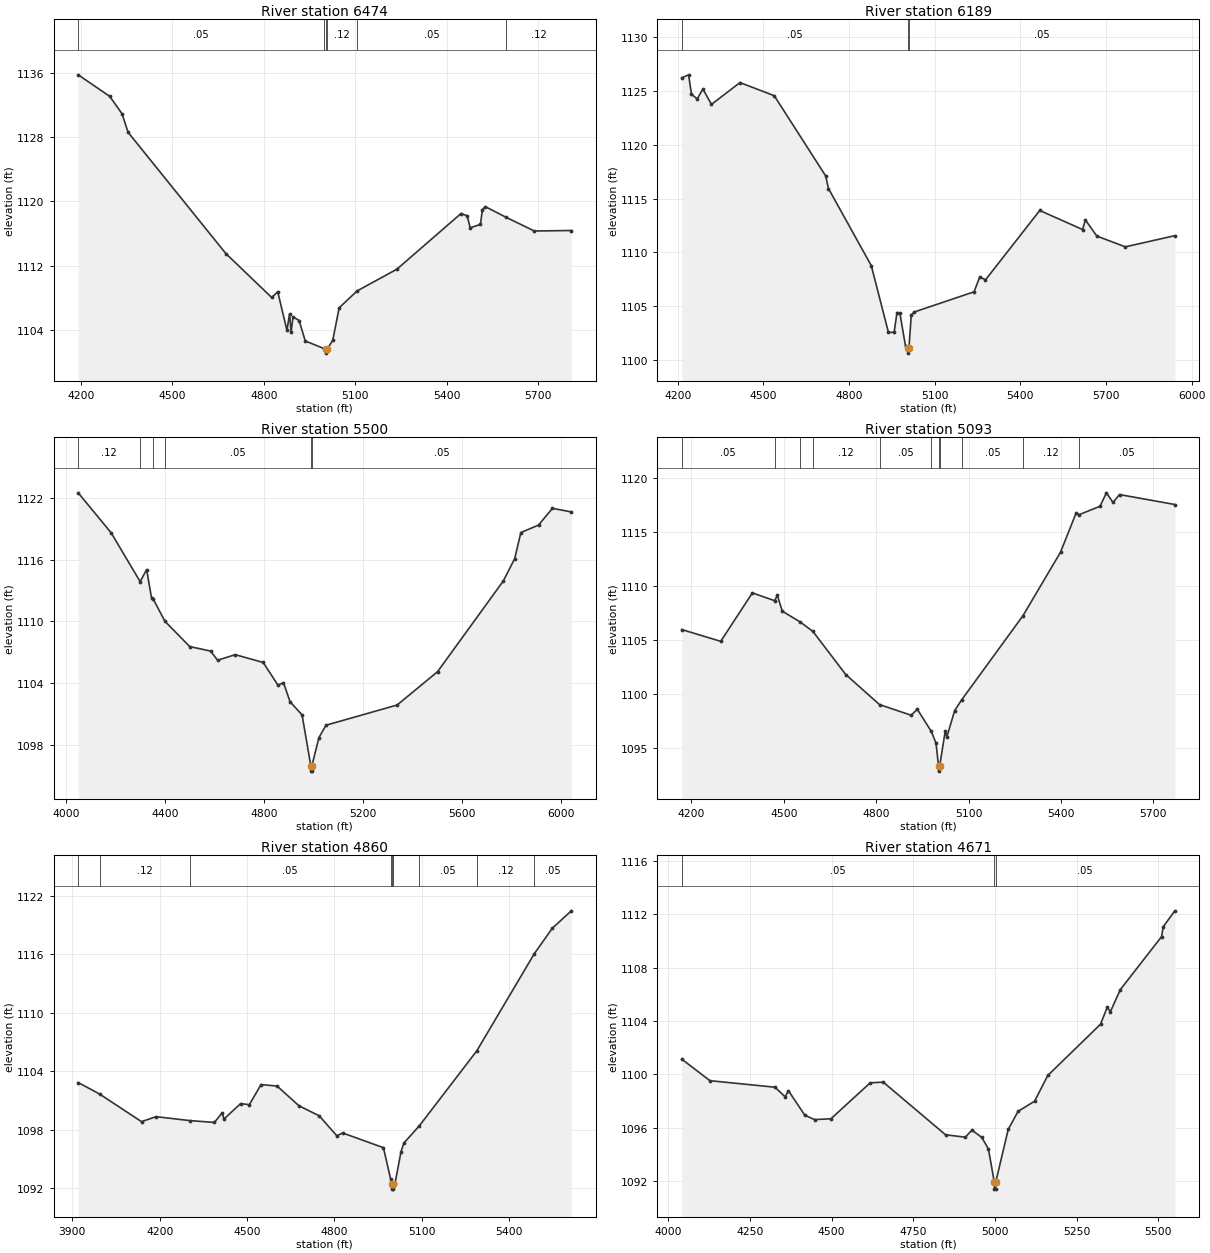
Type RM Length L Ch R = 1,6474,285,285,285
BEGIN DESCRIPTION:
Mapping XS 78cbf85f
END DESCRIPTION:
XS GIS Cut Line= 2
      2795679.12     10247302.99      2794064.47     10247198.82
#Sta/Elev= 30
  4190.6 1135.72  4294.2 1133.04  4334.3 1130.89  4354.4 1128.57  4675.0 1113.51
  4825.3 1108.05  4845.4 1108.74  4875.5 1103.97  4884.1 1106.01  4889.1 1103.72
  4895.5 1105.65  4915.5 1105.18  4935.6 1102.64  4996.6 1101.71  5003.7 1101.63
  5004.0 1101.13  5007.7 1101.63  5025.8 1102.73  5046.9 1106.77  5105.7 1108.86
  5236.2 1111.56  5446.6 1118.48  5466.7 1118.21  5476.7 1116.70  5510.4 1117.13
  5516.8 1118.96  5526.8 1119.33  5593.6 1118.03  5687.1 1116.31  5808.6 1116.37
#Mann=6,-1,0
  4190.6    0.05       0  4996.6    0.12       0  5003.7    0.07       0
  5007.7    0.12       0  5105.7    0.05       0  5593.6    0.12       0
Bank Sta=5003.7,5007.7
Exp/Cntr=0.3,0.1

Type RM Length L Ch R = 1,6189,689,689,689
BEGIN DESCRIPTION:
Mapping XS e62f53af
END DESCRIPTION:
XS GIS Cut Line= 2
      2795739.87     10247016.53      2794012.36     10246999.17
#Sta/Elev= 30
  4213.5 1126.22  4237.7 1126.50  4247.7 1124.70  4267.7 1124.26  4287.7 1125.18
  4317.7 1123.75  4417.7 1125.78  4537.7 1124.56  4717.7 1117.11  4727.7 1115.93
  4877.7 1108.76  4937.7 1102.56  4957.7 1102.56  4967.7 1104.40  4977.7 1104.37
  4997.7 1101.26  5005.7 1101.13  5006.0 1100.63  5009.7 1101.13  5017.7 1104.16
  5027.7 1104.45  5237.7 1106.33  5257.7 1107.72  5277.7 1107.44  5467.8 1113.89
  5617.8 1112.12  5627.8 1113.01  5667.8 1111.51  5767.8 1110.51  5941.1 1111.55
#Mann=3,-1,0
  4213.5    0.05       0  5005.7    0.03       0  5009.7    0.05       0
Bank Sta=5005.7,5009.7
Exp/Cntr=0.3,0.1

Type RM Length L Ch R = 1,5500,407,407,407
BEGIN DESCRIPTION:
SANFERNANDO039 11.0
END DESCRIPTION:
XS GIS Cut Line= 3
      2795655.66     10246603.11      2794726.49     10246397.69
      2793705.65     10246603.12
#Sta/Elev= 30
  4048.4 1122.51  4181.5 1118.62  4298.8 1113.86  4324.9 1115.04  4344.9 1112.26
  4352.1 1112.14  4399.0 1110.00  4499.0 1107.54  4583.6 1107.10  4611.6 1106.21
  4683.3 1106.75  4796.0 1105.99  4855.7 1103.78  4877.9 1104.03  4904.5 1102.17
  4953.2 1100.88  4988.6 1095.91  4988.8 1095.41  4992.3 1095.41  4992.6 1095.91
  5021.2 1098.67  5049.8 1099.88  5337.4 1101.85  5500.6 1105.09  5766.7 1113.94
  5812.5 1116.11  5837.3 1118.64  5908.7 1119.37  5965.0 1121.00  6041.3 1120.65
#Mann=6,-1,0
  4048.4    0.12       0  4298.8    0.05       0  4352.1    0.12       0
  4399.0    0.05       0  4988.6    0.03       0  4992.6    0.05       0
Bank Sta=4988.6,4992.6
Exp/Cntr=0.3,0.1

Type RM Length L Ch R = 1,5093,233,233,233
BEGIN DESCRIPTION:
Mapping XS c76c7d9d
END DESCRIPTION:
XS GIS Cut Line= 4
      2795192.99     10246408.91      2794819.69     10246200.56
      2793986.36     10246079.03      2793751.99     10246313.40
#Sta/Elev= 30
  4168.7 1105.99  4295.4 1104.90  4398.2 1109.38  4470.2 1108.66  4479.3 1109.14
  4495.3 1107.69  4553.9 1106.68  4594.9 1105.81  4701.3 1101.83  4811.0 1099.05
  4913.5 1098.07  4933.7 1098.62  4978.9 1096.58  4994.4 1095.49  5002.5 1093.40
  5002.7 1092.90  5006.5 1093.40  5024.3 1096.61  5029.4 1096.05  5055.0 1098.50
  5078.1 1099.51  5276.5 1107.26  5398.6 1113.14  5448.8 1116.73  5459.8 1116.62
  5526.6 1117.38  5547.8 1118.63  5569.0 1117.74  5590.2 1118.47  5769.8 1117.55
#Mann=11,-1,0
  4168.7    0.05       0  4470.2    0.12       0  4553.9    0.05       0
  4594.9    0.12       0  4811.0    0.05       0  4978.9    0.12       0
  5002.5    0.07       0  5006.5    0.12       0  5078.1    0.05       0
  5276.5    0.12       0  5459.8    0.05       0
Bank Sta=5002.5,5006.5
Exp/Cntr=0.3,0.1

Type RM Length L Ch R = 1,4860,189,189,189
BEGIN DESCRIPTION:
Mapping XS af4ca2f2
END DESCRIPTION:
XS GIS Cut Line= 3
      2795522.87     10245974.87      2794394.35     10245914.10
      2793830.90     10245888.10
#Sta/Elev= 30
  3920.2 1102.86  3993.8 1101.68  4137.7 1098.85  4187.8 1099.36  4303.0 1098.96
  4388.1 1098.77  4415.5 1099.77  4420.5 1099.11  4478.2 1100.70  4508.2 1100.59
  4548.3 1102.65  4603.6 1102.50  4678.5 1100.48  4748.6 1099.44  4808.7 1097.40
  4828.7 1097.69  4968.9 1096.18  4993.7 1092.94  4996.9 1092.43  4997.2 1091.93
  5000.7 1091.93  5000.9 1092.43  5009.0 1092.57  5029.0 1095.73  5039.0 1096.65
  5092.4 1098.43  5289.8 1106.12  5487.1 1116.07  5549.5 1118.70  5614.4 1120.47
#Mann=9,-1,0
  3920.2    0.05       0  3993.8    0.12       0  4303.0    0.05       0
  4993.7    0.12       0  4996.9    0.07       0  5000.9    0.12       0
  5092.4    0.05       0  5289.8    0.12       0  5487.1    0.05       0
Bank Sta=4996.9,5000.9
Exp/Cntr=0.3,0.1

Type RM Length L Ch R = 1,4671,1171,1171,1171
BEGIN DESCRIPTION:
Mapping XS a01f6f0d
END DESCRIPTION:
XS GIS Cut Line= 3
      2795462.05     10245801.25      2794698.17     10245766.53
      2793960.55     10245662.40
#Sta/Elev= 30
  4041.4 1101.14  4127.9 1099.52  4327.0 1099.03  4358.1 1098.31  4368.1 1098.77
  4418.2 1096.93  4448.2 1096.60  4498.2 1096.66  4618.4 1099.36  4658.4 1099.41
  4849.0 1095.46  4909.6 1095.28  4929.8 1095.81  4960.1 1095.26  4980.3 1094.40
  4998.5 1091.88  4998.7 1091.38  5002.2 1091.38  5002.5 1091.88  5040.9 1095.86
  5071.2 1097.22  5121.7 1097.98  5162.0 1099.91  5323.6 1103.76  5343.8 1105.02
  5353.9 1104.71  5384.2 1106.36  5510.3 1110.33  5515.5 1111.08  5551.0 1112.27
#Mann=3,-1,0
  4041.4    0.05       0  4998.5    0.03       0  5002.5    0.05       0
Bank Sta=4998.5,5002.5
Exp/Cntr=0.3,0.1

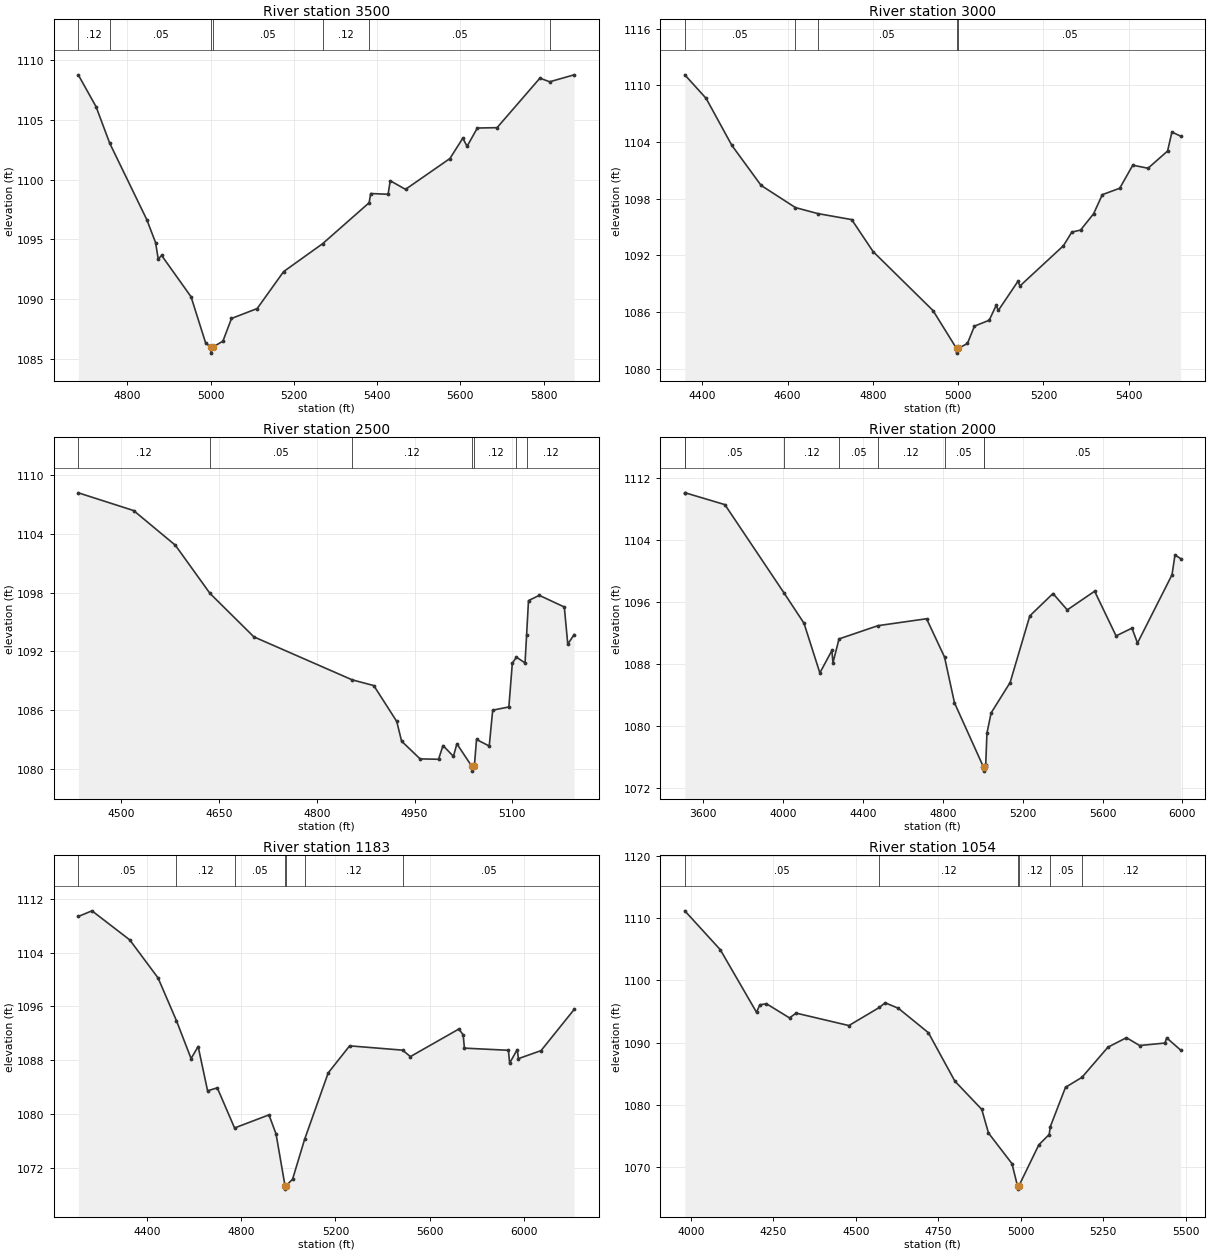
Type RM Length L Ch R = 1,3500,500,500,500
BEGIN DESCRIPTION:
SANFERNANDO039 7.0
END DESCRIPTION:
XS GIS Cut Line= 3
      2795305.67     10244803.13      2795054.57     10244997.60
      2794205.69     10245203.11
#Sta/Elev= 30
  4682.4 1108.76  4724.9 1106.11  4757.9 1103.04  4846.8 1096.66  4868.0 1094.73
  4874.3 1093.36  4882.5 1093.66  4953.1 1090.21  4988.4 1086.32  5001.1 1085.99
  5001.3 1085.49  5005.1 1085.99  5029.7 1086.49  5050.3 1088.39  5112.0 1089.22
  5175.5 1092.31  5269.4 1094.65  5380.9 1098.07  5384.7 1098.84  5426.5 1098.78
  5431.6 1099.91  5468.3 1099.19  5575.0 1101.77  5605.9 1103.47  5616.2 1102.79
  5640.8 1104.32  5688.2 1104.35  5791.1 1108.49  5814.7 1108.19  5873.4 1108.77
#Mann=7,-1,0
  4682.4    0.12       0  4757.9    0.05       0  5001.1    0.03       0
  5005.1    0.05       0  5269.4    0.12       0  5380.9    0.05       0
  5814.7    0.12       0
Bank Sta=5001.1,5005.1
Exp/Cntr=0.3,0.1

Type RM Length L Ch R = 1,3000,500,500,500
BEGIN DESCRIPTION:
SANFERNANDO039 6.0
END DESCRIPTION:
XS GIS Cut Line= 3
      2795355.65     10244703.11      2794717.02     10244650.36
      2794205.65     10244753.12
#Sta/Elev= 30
  4359.2 1111.11  4409.3 1108.61  4469.5 1103.64  4538.1 1099.40  4618.7 1097.05
  4670.7 1096.42  4750.5 1095.78  4800.7 1092.39  4941.1 1086.15  4996.2 1082.14
  4996.4 1081.64  5000.2 1082.14  5021.8 1082.66  5038.2 1084.50  5072.8 1085.12
  5089.1 1086.69  5094.2 1086.16  5140.0 1089.23  5145.1 1088.76  5246.8 1093.01
  5266.6 1094.46  5287.0 1094.67  5317.6 1096.40  5338.0 1098.42  5378.8 1099.10
  5409.4 1101.54  5445.2 1101.22  5491.0 1103.04  5501.2 1105.05  5521.6 1104.62
#Mann=5,-1,0
  4359.2    0.05       0  4618.7    0.12       0  4670.7    0.05       0
  4996.2    0.03       0  5000.2    0.05       0
Bank Sta=4996.2,5000.2
Exp/Cntr=0.3,0.1

Type RM Length L Ch R = 1,2500,500,500,500
BEGIN DESCRIPTION:
SANFERNANDO039 5.0
END DESCRIPTION:
XS GIS Cut Line= 3
      2795305.67     10244603.10      2794887.64     10244222.26
      2794705.64     10244153.10
#Sta/Elev= 30
  4434.5 1108.19  4519.3 1106.38  4583.3 1102.84  4636.3 1097.93  4703.7 1093.49
  4854.2 1089.11  4887.5 1088.52  4922.7 1084.86  4930.1 1082.85  4958.5 1081.04
  4986.8 1081.00  4993.6 1082.40  5009.6 1081.30  5014.9 1082.58  5037.7 1080.29
  5037.9 1079.79  5041.7 1080.29  5045.0 1083.02  5064.5 1082.35  5069.8 1086.01
  5094.6 1086.34  5099.9 1090.81  5106.2 1091.42  5119.4 1090.83  5121.8 1093.71
  5124.7 1097.19  5141.2 1097.73  5179.6 1096.54  5184.9 1092.75  5194.7 1093.73
#Mann=7,-1,0
  4434.5    0.12       0  4636.3    0.05       0  4854.2    0.12       0
  5037.7    0.07       0  5041.7    0.12       0  5106.2    0.05       0
  5121.8    0.12       0
Bank Sta=5037.7,5041.7
Exp/Cntr=0.3,0.1

Type RM Length L Ch R = 1,2000,817,817,817
BEGIN DESCRIPTION:
SANFERNANDO039 4.0
END DESCRIPTION:
XS GIS Cut Line= 3
      2796105.66     10244253.10      2794671.86     10243839.73
      2794105.70     10244653.09
#Sta/Elev= 30
  3507.8 1110.09  3510.3 1110.09  3708.5 1108.57  4005.2 1097.17  4104.8 1093.28
  4184.2 1086.88  4244.6 1089.77  4249.8 1088.18  4280.2 1091.26  4475.5 1092.97
  4718.6 1093.86  4808.5 1088.93  4858.5 1083.02  5004.1 1074.72  5004.4 1074.22
  5008.1 1074.72  5014.9 1075.00  5021.0 1079.11  5041.9 1081.72  5137.1 1085.64
  5235.7 1094.23  5351.8 1097.11  5423.3 1095.00  5560.3 1097.41  5667.7 1091.65
  5747.4 1092.65  5775.0 1090.73  5947.8 1099.52  5962.7 1102.07  5991.0 1101.62
#Mann=8,-1,0
  3507.8    0.12       0  3510.3    0.05       0  4005.2    0.12       0
  4280.2    0.05       0  4475.5    0.12       0  4808.5    0.05       0
  5004.1    0.05       0  5008.1    0.05       0
Bank Sta=5004.1,5008.1
Exp/Cntr=0.3,0.1

Type RM Length L Ch R = 1,1183,129,129,129
BEGIN DESCRIPTION:
Mapping XS 056bd715
END DESCRIPTION:
XS GIS Cut Line= 6
      2795913.48     10243405.42      2795219.00     10243396.74
      2794984.62     10243396.74      2794715.53     10243431.46
      2794533.24     10243509.59      2794316.23     10244177.98
#Sta/Elev= 30
  4110.2 1109.39  4168.0 1110.23  4328.0 1105.91  4448.0 1100.25  4526.1 1093.88
  4588.0 1088.25  4618.0 1090.04  4658.0 1083.45  4699.1 1083.89  4772.3 1077.92
  4918.1 1079.87  4948.1 1077.03  4986.1 1069.32  4986.3 1068.82  4990.1 1069.32
  5018.1 1070.29  5069.0 1076.21  5169.1 1086.11  5259.9 1090.14  5484.4 1089.50
  5517.4 1088.54  5722.7 1092.64  5741.1 1091.79  5746.4 1089.80  5932.9 1089.48
  5938.1 1087.57  5970.1 1089.58  5975.4 1088.24  6071.2 1089.43  6211.5 1095.56
#Mann=7,-1,0
  4110.2    0.05       0  4526.1    0.12       0  4772.3    0.05       0
  4986.1    0.05       0  4990.1    0.05       0  5069.0    0.12       0
  5484.4    0.05       0
Bank Sta=4986.1,4990.1
Exp/Cntr=0.3,0.1

Type RM Length L Ch R = 1,1054,92,92,92
BEGIN DESCRIPTION:
Mapping XS f0016b4c
END DESCRIPTION:
XS GIS Cut Line= 5
      2796053.17     10243205.88      2795318.74     10243216.30
      2794959.37     10243284.01      2794730.20     10243398.59
      2794594.83     10243455.87
#Sta/Elev= 30
  3981.6 1111.19  4089.1 1104.95  4199.1 1094.88  4209.1 1096.08  4229.1 1096.26
  4299.1 1093.98  4319.1 1094.75  4479.1 1092.75  4571.5 1095.66  4589.1 1096.41
  4629.1 1095.53  4720.2 1091.60  4800.6 1083.81  4882.0 1079.28  4902.4 1075.48
  4973.6 1070.56  4990.4 1066.96  4990.7 1066.46  4994.4 1066.96  5055.0 1073.58
  5086.4 1075.24  5090.0 1076.52  5136.0 1082.83  5185.9 1084.43  5264.5 1089.27
  5320.7 1090.80  5360.8 1089.54  5437.3 1089.94  5442.8 1090.77  5485.0 1088.81
#Mann=6,-1,0
  3981.6    0.05       0  4571.5    0.12       0  4990.4    0.07       0
  4994.4    0.12       0  5090.0    0.05       0  5185.9    0.12       0
Bank Sta=4990.4,4994.4
Exp/Cntr=0.3,0.1

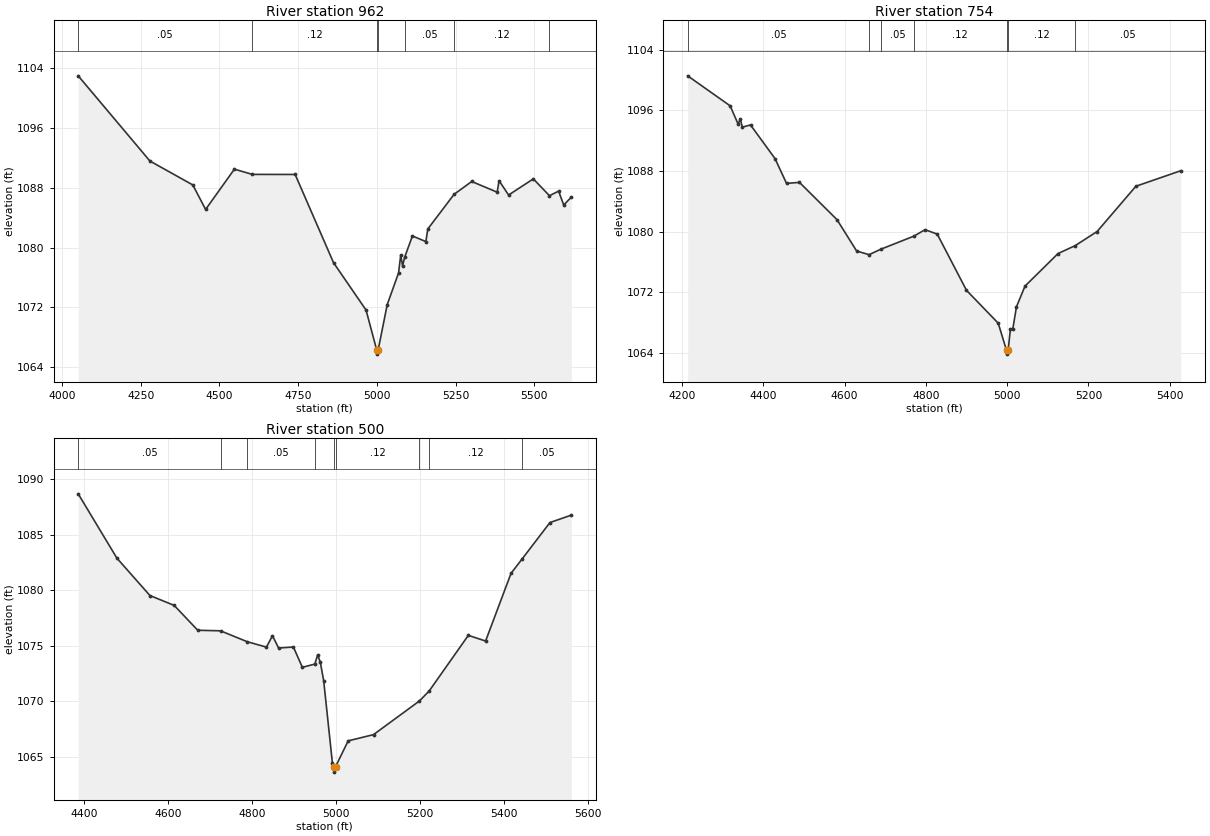
Type RM Length L Ch R = 1,962,208,208,208
BEGIN DESCRIPTION:
Mapping XS 7a58bee0
END DESCRIPTION:
XS GIS Cut Line= 5
      2795954.15     10242997.55      2795058.33     10243159.01
      2794751.04     10243341.30      2794573.95     10243455.88
      2794495.84     10243497.55
#Sta/Elev= 30
  4051.0 1102.99  4278.9 1091.59  4415.2 1088.39  4455.9 1085.11  4547.3 1090.50
  4604.5 1089.80  4740.4 1089.79  4862.3 1077.99  4965.7 1071.65  4999.9 1066.25
  5000.1 1065.75  5003.9 1066.25  5033.1 1072.39  5069.0 1076.61  5075.9 1079.01
  5081.8 1077.55  5088.3 1078.70  5113.0 1081.56  5155.8 1080.81  5162.0 1082.50
  5245.4 1087.13  5301.5 1088.85  5382.4 1087.42  5388.4 1088.95  5418.7 1087.04
  5497.2 1089.20  5548.5 1086.95  5577.6 1087.56  5593.9 1085.70  5618.0 1086.76
#Mann=7,-1,0
  4051.0    0.05       0  4604.5    0.12       0  4999.9    0.07       0
  5003.9    0.12       0  5088.3    0.05       0  5245.4    0.12       0
  5548.5    0.05       0
Bank Sta=4999.9,5003.9
Exp/Cntr=0.3,0.1

Type RM Length L Ch R = 1,754,254,254,254
BEGIN DESCRIPTION:
Mapping XS a00d370b
END DESCRIPTION:
XS GIS Cut Line= 5
      2795719.83     10242737.13      2795292.70     10242773.59
      2794943.74     10243007.97      2794803.12     10243278.80
      2794752.62     10243309.10
#Sta/Elev= 30
  4214.0 1100.58  4318.5 1096.62  4338.3 1094.19  4343.4 1094.90  4348.6 1093.80
  4368.7 1094.09  4428.9 1089.65  4457.3 1086.37  4489.1 1086.50  4581.4 1081.58
  4629.7 1077.44  4660.3 1076.95  4689.2 1077.67  4770.7 1079.40  4798.0 1080.25
  4828.0 1079.67  4900.0 1072.24  4978.0 1067.90  4998.5 1064.31  4998.7 1063.81
  5002.5 1064.31  5008.0 1067.14  5014.0 1067.18  5023.0 1070.07  5044.0 1072.80
  5125.2 1077.10  5167.6 1078.15  5221.3 1080.01  5316.7 1085.99  5427.1 1088.04
#Mann=7,-1,0
  4214.0    0.05       0  4660.3    0.12       0  4689.2    0.05       0
  4770.7    0.12       0  4998.5    0.07       0  5002.5    0.12       0
  5167.6    0.05       0
Bank Sta=4998.5,5002.5
Exp/Cntr=0.3,0.1

Type RM Length L Ch R = 1,500,0,0,0
BEGIN DESCRIPTION:
SANFERNANDO039 1.0
END DESCRIPTION:
XS GIS Cut Line= 4
      2795305.69     10242253.10      2794926.26     10242736.72
      2794810.38     10243233.00      2794770.83     10243264.02
#Sta/Elev= 30
  4385.3 1088.70  4477.5 1082.90  4556.2 1079.53  4614.0 1078.64  4670.1 1076.40
  4724.3 1076.35  4787.7 1075.37  4833.7 1074.88  4848.1 1075.91  4862.6 1074.80
  4897.9 1074.89  4919.2 1073.06  4948.9 1073.35  4955.7 1074.18  4962.0 1073.52
  4970.0 1071.86  4990.9 1064.40  4994.4 1064.11  4994.7 1063.61  4998.4 1064.11
  5028.4 1066.43  5088.7 1066.99  5197.9 1070.02  5221.2 1070.92  5314.6 1075.94
  5355.7 1075.43  5416.3 1081.53  5441.7 1082.78  5509.0 1086.11  5559.9 1086.78
#Mann=9,-1,0
  4385.3    0.05       0  4724.3    0.12       0  4787.7    0.05       0
  4948.9    0.12       0  4994.4    0.07       0  4998.4    0.12       0
  5197.9    0.05       0  5221.2    0.12       0  5441.7    0.05       0
Bank Sta=4994.4,4998.4
Exp/Cntr=0.3,0.1

Chan Stop Cuts=-1