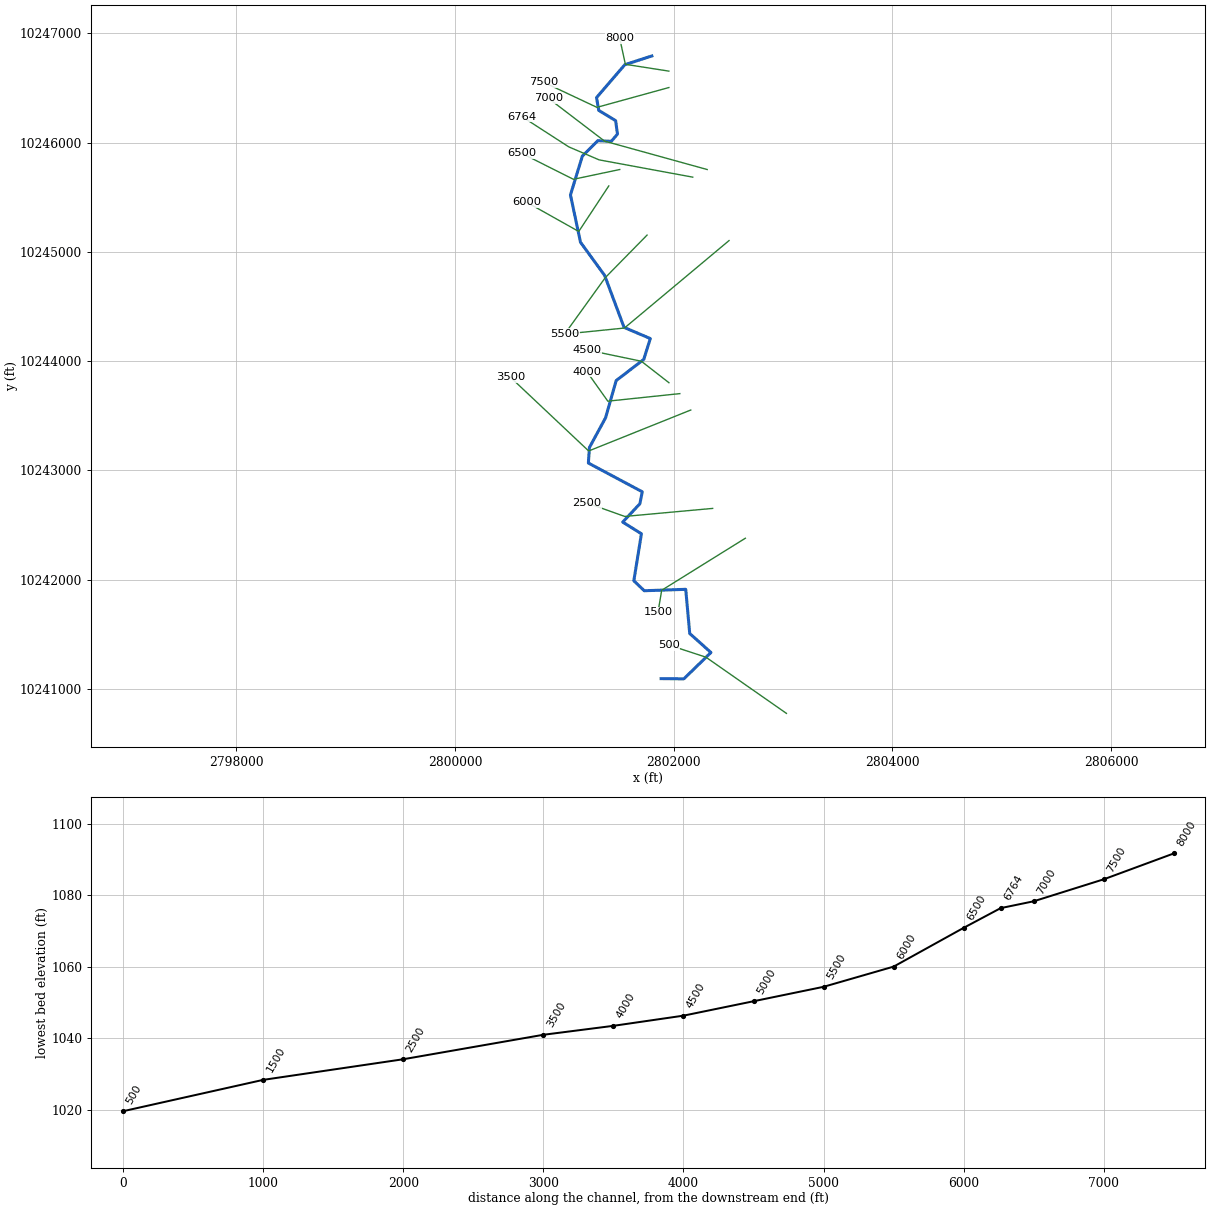
--- SANFERNANDO040.prj (project) ---

Proj Title=SANFERNANDO040 Base Level Engineering
Current Plan=p01
Default Exp/Contr=0.3,0.1
English Units
Geom File=g01
Flow File=f01
Plan File=p01
BEGIN DESCRIPTION:
SANFERNANDO040
END DESCRIPTION:

--- SANFERNANDO040.p01 (plan) ---

Plan Title=Multiple Run
Short Identifier=Multiple
Geom File=g01
Flow File=f01
Subcritical Flow
K Sum by GR= 0
Std Step Tol= 0.01
Critical Tol= 0.01
Num of Std Step Trials= 20
Max Error Tol= 0.3
Flow Tol Ratio= 0.001
Split Flow NTrial= 30
Split Flow Tol= 0.02
Split Flow Ratio= 0.02
Log Output Level= 0
Friction Slope Method= 1
Unsteady Friction Slope Method= 2
Unsteady Bridges Friction Slope Method= 1
Parabolic Critical Depth
Global Vel Dist=  1 , 1 , 1
Global Log Level= 0
CheckData=True
Encroach Param= -1, 0, 0, 0
BEGIN DESCRIPTION:
Multiple Run
END DESCRIPTION:

--- SANFERNANDO040.f01 (steady flow) ---

Flow Title=Multiple
Number of Profiles=7
Profile Names=10-year,25-year,50-year,1pct_min,100-year,1pct_plu,500-year
River Rch & RM= SANFERNANDO040,Reach-1,8000
     394     638     805     609    1068    1871    1472
Boundary for River Rch & Prof#=SANFERNANDO040,Reach-1,1
Up Type=0
Dn Type=3
Dn Slope=0.005
Boundary for River Rch & Prof#=SANFERNANDO040,Reach-1,2
Up Type=0
Dn Type=3
Dn Slope=0.005
Boundary for River Rch & Prof#=SANFERNANDO040,Reach-1,3
Up Type=0
Dn Type=3
Dn Slope=0.005
Boundary for River Rch & Prof#=SANFERNANDO040,Reach-1,4
Up Type=0
Dn Type=3
Dn Slope=0.005
Boundary for River Rch & Prof#=SANFERNANDO040,Reach-1,5
Up Type=0
Dn Type=3
Dn Slope=0.005
Boundary for River Rch & Prof#=SANFERNANDO040,Reach-1,6
Up Type=0
Dn Type=3
Dn Slope=0.005
Boundary for River Rch & Prof#=SANFERNANDO040,Reach-1,7
Up Type=0
Dn Type=3
Dn Slope=0.005

--- SANFERNANDO040.g01 (geometry) ---

Geom Title=Existing Conditions

River Reach=SANFERNANDO040,Reach-1
Reach XY= 30
      2801799.50     10246792.00      2801552.50     10246712.00
      2801293.25     10246411.00      2801314.00     10246294.00
      2801468.25     10246200.00      2801485.00     10246077.00
      2801428.75     10246011.00      2801305.75     10246017.00
      2801164.00     10245876.00      2801055.00     10245521.00
      2801146.75     10245088.00      2801368.00     10244784.00
      2801545.25     10244309.00      2801785.50     10244207.00
      2801725.50     10244016.00      2801473.00     10243822.00
      2801376.25     10243482.00      2801228.50     10243210.00
      2801219.00     10243068.00      2801712.00     10242805.00
      2801690.25     10242696.00      2801533.25     10242528.00
      2801704.25     10242421.00      2801634.75     10241991.00
      2801730.25     10241900.00      2802109.50     10241913.00
      2802146.00     10241509.00      2802340.25     10241335.00
      2802092.25     10241094.00      2801884.75     10241096.00

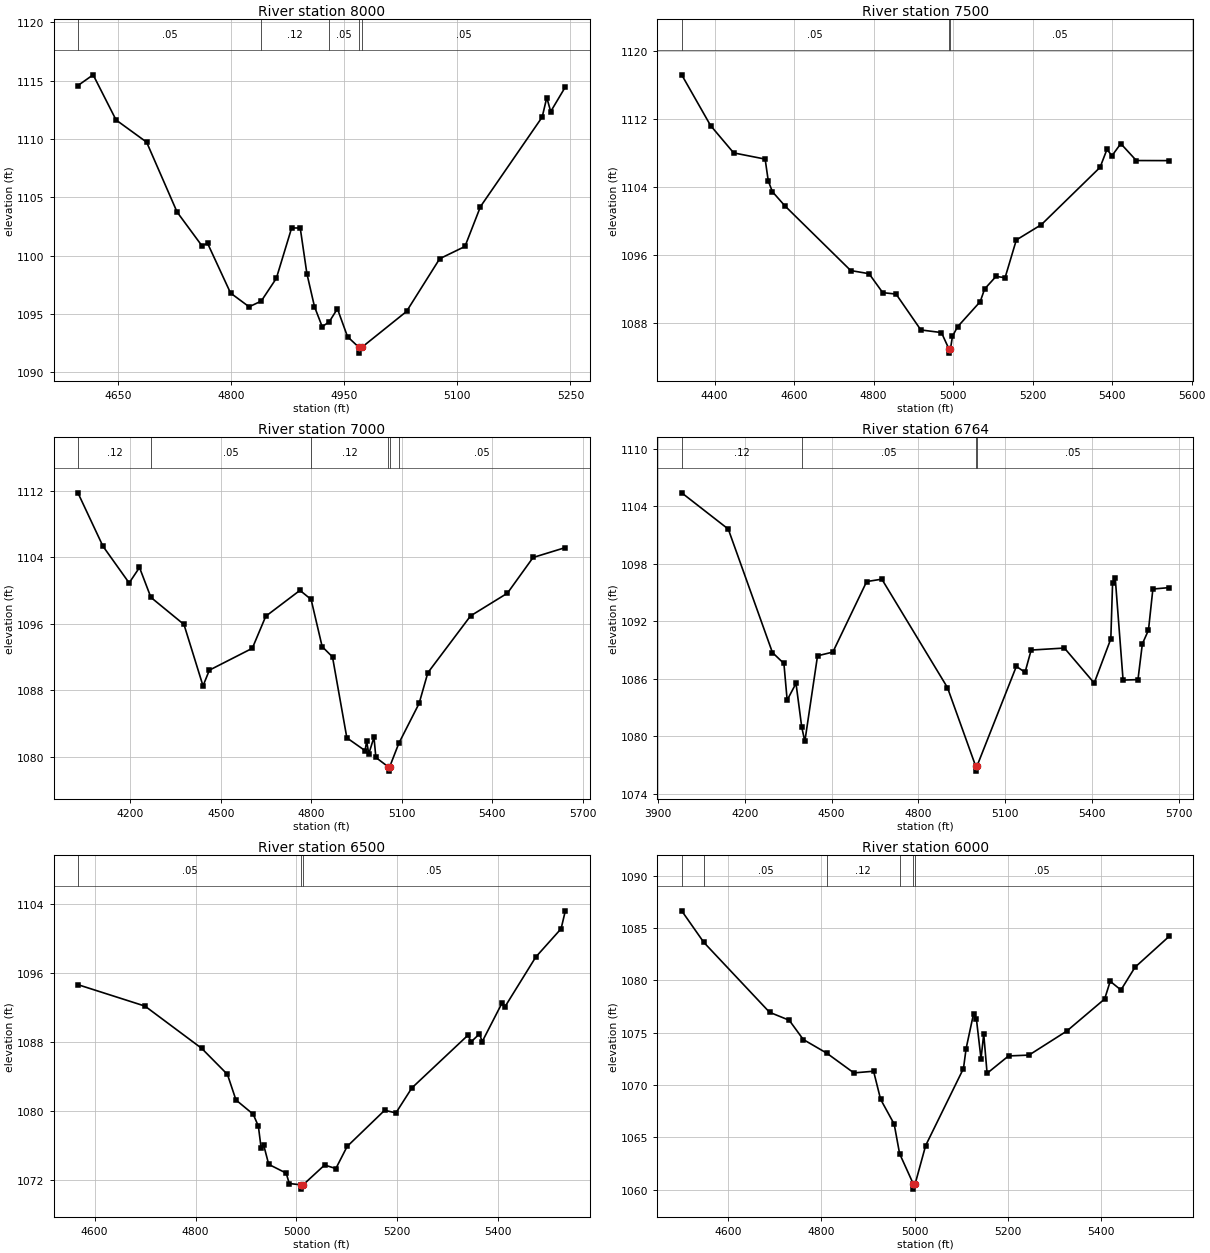
Type RM Length L Ch R = 1,8000,500,500,500
BEGIN DESCRIPTION:
SANFERNANDO040 16.0
END DESCRIPTION:
XS GIS Cut Line= 3
      2801955.65     10246653.12      2801557.49     10246715.42
      2801505.68     10246953.14
#Sta/Elev= 30
  4597.0 1114.59  4617.2 1115.51  4647.6 1111.64  4688.1 1109.74  4728.5 1103.75
  4761.3 1100.87  4769.0 1101.06  4799.4 1096.81  4824.0 1095.63  4840.1 1096.12
  4860.1 1098.07  4880.4 1102.39  4891.8 1102.38  4900.6 1098.48  4910.7 1095.64
  4920.9 1093.93  4930.2 1094.34  4941.1 1095.46  4954.5 1093.07  4969.5 1092.16
  4969.7 1091.66  4973.5 1092.16  5032.7 1095.23  5076.7 1099.75  5110.2 1100.80
  5130.8 1104.22  5212.6 1111.89  5218.7 1113.56  5223.9 1112.36  5243.3 1114.47
#Mann=5,-1,0
  4597.0    0.05       0  4840.1    0.12       0  4930.2    0.05       0
  4969.5    0.05       0  4973.5    0.05       0
Bank Sta=4969.5,4973.5
Exp/Cntr=0.3,0.1

Type RM Length L Ch R = 1,7500,500,500,500
BEGIN DESCRIPTION:
SANFERNANDO040 15.0
END DESCRIPTION:
XS GIS Cut Line= 3
      2801955.66     10246503.10      2801297.27     10246321.78
      2800805.68     10246553.11
#Sta/Elev= 30
  4317.1 1117.20  4389.7 1111.23  4447.8 1108.01  4527.0 1107.28  4534.9 1104.70
  4545.3 1103.44  4576.4 1101.79  4742.3 1094.16  4788.4 1093.79  4822.8 1091.56
  4856.4 1091.39  4918.7 1087.17  4970.5 1086.86  4989.3 1084.94  4989.5 1084.44
  4993.3 1084.94  4998.2 1086.42  5011.1 1087.54  5068.1 1090.50  5079.1 1091.99
  5107.8 1093.47  5130.6 1093.32  5158.9 1097.76  5221.8 1099.56  5369.6 1106.31
  5386.8 1108.41  5399.6 1107.68  5421.7 1109.10  5460.8 1107.11  5543.3 1107.10
#Mann=3,-1,0
  4317.1    0.05       0  4989.3    0.05       0  4993.3    0.05       0
Bank Sta=4989.3,4993.3
Exp/Cntr=0.3,0.1

Type RM Length L Ch R = 1,7000,236,236,236
BEGIN DESCRIPTION:
SANFERNANDO040 14.0
END DESCRIPTION:
XS GIS Cut Line= 3
      2802305.70     10245753.11      2801366.78     10246012.90
      2800855.71     10246403.09
#Sta/Elev= 30
  4025.8 1111.74  4108.8 1105.33  4195.8 1100.91  4230.1 1102.77  4267.9 1099.18
  4377.7 1095.92  4440.9 1088.54  4461.9 1090.43  4604.4 1093.06  4649.1 1096.91
  4762.5 1100.02  4799.5 1098.93  4836.2 1093.26  4870.5 1092.02  4918.1 1082.30
  4978.6 1080.76  4983.8 1081.91  4990.8 1080.37  5008.1 1082.37  5014.4 1079.94
  5056.0 1078.80  5056.3 1078.30  5060.0 1078.80  5090.4 1081.63  5157.8 1086.43
  5186.8 1090.12  5328.5 1096.95  5450.8 1099.68  5536.0 1103.97  5643.0 1105.16
#Mann=6,-1,0
  4025.8    0.12       0  4267.9    0.05       0  4799.5    0.12       0
  5056.0    0.07       0  5060.0    0.12       0  5090.4    0.05       0
Bank Sta=5056,5060
Exp/Cntr=0.3,0.1

Type RM Length L Ch R = 1,6764,264,264,264
BEGIN DESCRIPTION:
Mapping XS 3beeaa3e
END DESCRIPTION:
XS GIS Cut Line= 4
      2802173.78     10245683.32      2801316.74     10245841.54
      2801039.86     10245960.21      2800611.30     10246237.12
#Sta/Elev= 30
  3982.6 1105.40  4143.4 1101.62  4295.9 1088.75  4335.5 1087.61  4346.7 1083.79
  4377.3 1085.54  4397.1 1080.97  4407.8 1079.49  4451.6 1088.41  4504.5 1088.80
  4621.3 1096.15  4673.6 1096.40  4900.2 1085.10  4997.9 1076.89  4998.2 1076.39
  5001.9 1076.89  5138.1 1087.31  5168.1 1086.69  5189.2 1089.01  5304.0 1089.22
  5406.9 1085.57  5464.3 1090.18  5470.3 1095.95  5479.5 1096.53  5506.6 1085.88
  5558.0 1085.93  5573.2 1089.66  5594.3 1091.09  5609.5 1095.37  5665.6 1095.52
#Mann=4,-1,0
  3982.6    0.12       0  4397.1    0.05       0  4997.9    0.05       0
  5001.9    0.05       0
Bank Sta=4997.9,5001.9
Exp/Cntr=0.3,0.1

Type RM Length L Ch R = 1,6500,500,500,500
BEGIN DESCRIPTION:
SANFERNANDO040 13.0
END DESCRIPTION:
XS GIS Cut Line= 3
      2801505.70     10245753.12      2801081.83     10245663.68
      2800605.65     10245903.13
#Sta/Elev= 30
  4566.8 1094.65  4699.7 1092.16  4812.1 1087.25  4863.2 1084.22  4880.1 1081.25
  4914.3 1079.59  4924.5 1078.21  4929.9 1075.70  4935.0 1076.02  4945.0 1073.77
  4979.6 1072.75  4985.8 1071.54  5009.2 1071.39  5009.4 1070.89  5013.2 1071.39
  5055.8 1073.69  5078.1 1073.28  5100.5 1075.85  5174.8 1080.05  5197.2 1079.75
  5228.8 1082.65  5340.4 1088.80  5346.0 1087.99  5362.7 1088.92  5368.3 1088.04
  5407.4 1092.50  5413.0 1092.05  5474.4 1097.86  5524.6 1101.15  5533.0 1103.23
#Mann=3,-1,0
  4566.8    0.05       0  5009.2    0.05       0  5013.2    0.05       0
Bank Sta=5009.2,5013.2
Exp/Cntr=0.3,0.1

Type RM Length L Ch R = 1,6000,500,500,500
BEGIN DESCRIPTION:
SANFERNANDO040 12.0
END DESCRIPTION:
XS GIS Cut Line= 3
      2801405.66     10245603.08      2801130.97     10245186.50
      2800655.65     10245453.13
#Sta/Elev= 30
  4501.0 1086.64  4548.3 1083.63  4689.2 1076.95  4731.3 1076.19  4761.4 1074.35
  4811.9 1073.04  4869.8 1071.16  4912.0 1071.32  4927.0 1068.64  4956.1 1066.27
  4967.7 1063.45  4997.0 1060.56  4997.3 1060.06  5001.0 1060.56  5023.5 1064.22
  5104.5 1071.58  5110.2 1073.49  5126.2 1076.83  5132.2 1076.32  5142.1 1072.51
  5147.9 1074.88  5155.1 1071.12  5201.0 1072.78  5244.8 1072.86  5325.9 1075.16
  5406.9 1078.22  5418.8 1079.91  5441.8 1079.08  5471.9 1081.25  5545.0 1084.20
#Mann=6,-1,0
  4501.0    0.12       0  4548.3    0.05       0  4811.9    0.12       0
  4967.7    0.05       0  4997.0    0.03       0  5001.0    0.05       0
Bank Sta=4997,5001
Exp/Cntr=0.3,0.1

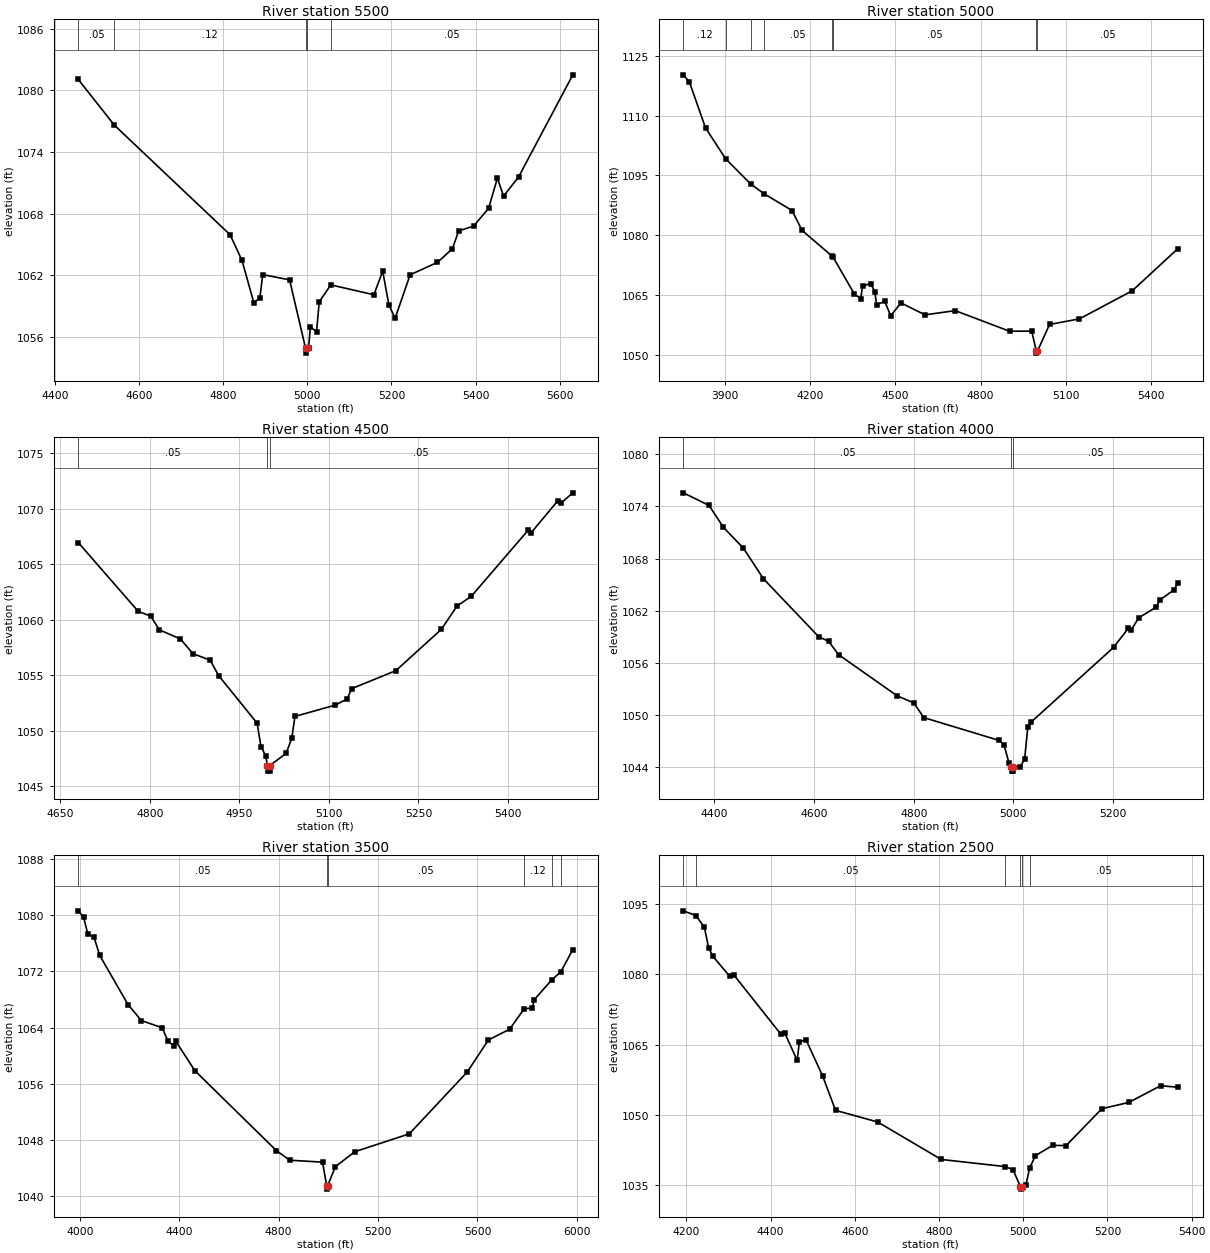
Type RM Length L Ch R = 1,5500,500,500,500
BEGIN DESCRIPTION:
SANFERNANDO040 11.0
END DESCRIPTION:
XS GIS Cut Line= 3
      2801755.70     10245153.13      2801374.35     10244765.03
      2801005.66     10244253.08
#Sta/Elev= 30
  4455.9 1081.05  4541.9 1076.59  4816.6 1065.94  4844.9 1063.44  4873.2 1059.30
  4887.3 1059.81  4894.3 1062.06  4958.0 1061.55  4995.8 1054.92  4996.1 1054.42
  4999.8 1054.92  5003.1 1054.92  5007.4 1056.98  5022.1 1056.50  5028.3 1059.41
  5055.9 1061.06  5158.3 1060.10  5179.2 1062.40  5193.9 1059.11  5208.7 1057.81
  5244.3 1062.04  5309.3 1063.25  5344.9 1064.58  5359.6 1066.31  5395.2 1066.78
  5430.8 1068.51  5451.7 1071.44  5466.4 1069.70  5502.0 1071.56  5630.9 1081.50
#Mann=5,-1,0
  4455.9    0.05       0  4541.9    0.12       0  4995.8    0.07       0
  4999.8    0.12       0  5055.9    0.05       0
Bank Sta=4995.8,4999.8
Exp/Cntr=0.3,0.1

Type RM Length L Ch R = 1,5000,500,500,500
BEGIN DESCRIPTION:
SANFERNANDO040 10.0
END DESCRIPTION:
XS GIS Cut Line= 3
      2802505.70     10245103.12      2801548.77     10244303.10
      2801055.69     10244253.11
#Sta/Elev= 30
  3752.7 1120.24  3774.2 1118.41  3830.9 1106.93  3901.8 1099.16  3990.2 1092.85
  4035.8 1090.45  4136.0 1086.18  4171.1 1081.20  4276.3 1074.77  4280.9 1074.42
  4355.9 1065.17  4378.0 1064.10  4384.5 1067.29  4413.1 1067.81  4427.5 1065.80
  4434.0 1062.53  4462.6 1063.40  4483.4 1059.77  4519.8 1062.99  4604.4 1060.00
  4711.1 1061.05  4902.5 1055.88  4980.5 1055.92  4996.7 1050.89  4997.0 1050.39
  5000.7 1050.89  5043.3 1057.58  5148.7 1058.99  5334.8 1066.04  5495.6 1076.62
#Mann=8,-1,0
  3752.7    0.12       0  3901.8    0.05       0  3990.2    0.12       0
  4035.8    0.05       0  4276.3    0.12       0  4280.9    0.05       0
  4996.7    0.05       0  5000.7    0.05       0
Bank Sta=4996.7,5000.7
Exp/Cntr=0.3,0.1

Type RM Length L Ch R = 1,4500,500,500,500
BEGIN DESCRIPTION:
SANFERNANDO040 9.0
END DESCRIPTION:
XS GIS Cut Line= 3
      2801955.72     10243803.08      2801703.44     10243999.46
      2801205.72     10244103.10
#Sta/Elev= 30
  4680.3 1066.97  4780.8 1060.76  4801.6 1060.34  4816.1 1059.10  4851.4 1058.28
  4872.2 1056.96  4901.1 1056.37  4915.6 1054.96  4979.8 1050.69  4986.2 1048.58
  4994.3 1047.74  4996.9 1046.87  4997.2 1046.37  5000.7 1046.37  5000.9 1046.87
  5028.4 1047.97  5037.9 1049.36  5043.1 1051.30  5110.1 1052.31  5130.5 1052.87
  5138.1 1053.80  5212.2 1055.43  5288.3 1059.15  5314.4 1061.24  5338.3 1062.12
  5433.3 1068.06  5438.4 1067.84  5483.4 1070.74  5488.5 1070.52  5508.4 1071.45
#Mann=3,-1,0
  4680.3    0.05       0  4996.9    0.05       0  5000.9    0.05       0
Bank Sta=4996.9,5000.9
Exp/Cntr=0.3,0.1

Type RM Length L Ch R = 1,4000,500,500,500
BEGIN DESCRIPTION:
SANFERNANDO040 8.0
END DESCRIPTION:
XS GIS Cut Line= 3
      2802055.71     10243703.11      2801396.83     10243633.96
      2801205.69     10243903.10
#Sta/Elev= 30
  4337.5 1075.56  4389.1 1074.11  4418.0 1071.59  4458.2 1069.18  4498.4 1065.66
  4609.0 1059.01  4629.1 1058.47  4649.2 1056.93  4766.8 1052.19  4800.1 1051.38
  4820.2 1049.69  4971.0 1047.07  4981.0 1046.57  4991.1 1044.48  4996.1 1044.03
  4996.3 1043.53  4999.8 1043.53  5000.1 1044.03  5014.0 1044.06  5022.6 1044.93
  5028.8 1048.59  5035.8 1049.19  5201.0 1057.77  5230.5 1059.96  5236.6 1059.78
  5251.4 1061.17  5287.1 1062.42  5293.3 1063.20  5322.7 1064.41  5330.1 1065.21
#Mann=3,-1,0
  4337.5    0.05       0  4996.1    0.05       0  5000.1    0.05       0
Bank Sta=4996.1,5000.1
Exp/Cntr=0.3,0.1

Type RM Length L Ch R = 1,3500,1000,1000,1000
BEGIN DESCRIPTION:
SANFERNANDO040 7.0
END DESCRIPTION:
XS GIS Cut Line= 3
      2802155.65     10243553.10      2801221.71     10243178.40
      2800505.71     10243853.09
#Sta/Elev= 30
  3993.7 1080.61  4015.2 1079.69  4032.7 1077.25  4056.9 1076.87  4079.9 1074.28
  4194.0 1067.27  4247.8 1065.00  4331.2 1063.98  4355.4 1062.04  4379.6 1061.38
  4385.0 1062.12  4463.0 1057.87  4791.2 1046.50  4844.9 1045.14  4976.7 1044.87
  4993.2 1041.53  4993.4 1041.03  4997.2 1041.53  5028.8 1044.24  5106.5 1046.35
  5325.8 1048.89  5559.2 1057.70  5644.2 1062.25  5729.2 1063.76  5788.8 1066.71
  5821.0 1066.76  5828.3 1067.96  5899.1 1070.79  5935.8 1071.95  5983.8 1075.10
#Mann=6,-1,0
  3993.7    0.05       0  4993.2    0.03       0  4997.2    0.05       0
  5788.8    0.12       0  5899.1    0.05       0  5935.8    0.12       0
Bank Sta=4993.2,4997.2
Exp/Cntr=0.3,0.1

Type RM Length L Ch R = 1,2500,1000,1000,1000
BEGIN DESCRIPTION:
SANFERNANDO040 5.0
END DESCRIPTION:
XS GIS Cut Line= 3
      2802355.73     10242653.12      2801551.57     10242579.65
      2801205.65     10242703.12
#Sta/Elev= 30
  4192.5 1093.57  4222.5 1092.56  4242.6 1090.04  4252.8 1085.60  4262.8 1083.86
  4303.0 1079.57  4313.0 1079.84  4423.5 1067.33  4433.5 1067.49  4463.0 1061.66
  4468.0 1065.56  4483.7 1066.12  4523.9 1058.23  4554.0 1051.01  4654.5 1048.51
  4805.1 1040.53  4957.8 1039.00  4975.8 1038.31  4993.4 1034.70  4993.7 1034.20
  4997.4 1034.70  5006.3 1035.10  5015.2 1038.70  5029.0 1041.36  5070.0 1043.53
  5101.8 1043.49  5186.8 1051.36  5250.5 1052.69  5326.4 1056.26  5367.3 1055.93
#Mann=6,-1,0
  4192.5    0.12       0  4222.5    0.05       0  4957.8    0.12       0
  4993.4    0.07       0  4997.4    0.12       0  5015.2    0.05       0
Bank Sta=4993.4,4997.4
Exp/Cntr=0.3,0.1

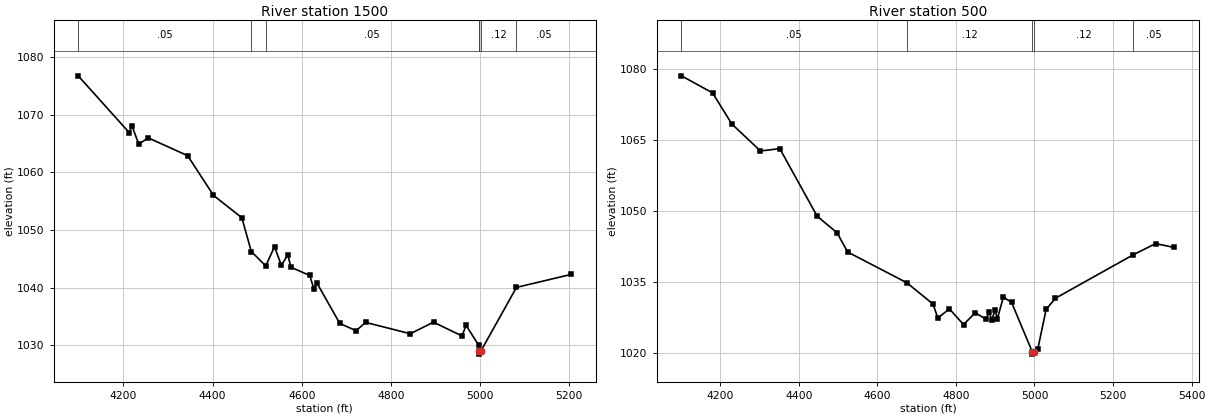
Type RM Length L Ch R = 1,1500,1000,1000,1000
BEGIN DESCRIPTION:
SANFERNANDO040 3.0
END DESCRIPTION:
XS GIS Cut Line= 3
      2802655.00     10242380.43      2801889.75     10241904.25
      2801855.68     10241703.12
#Sta/Elev= 30
  4098.7 1076.74  4213.2 1066.88  4219.1 1068.09  4234.5 1064.88  4255.7 1065.98
  4344.2 1062.88  4402.1 1056.00  4465.8 1052.10  4486.9 1046.24  4519.3 1043.76
  4539.0 1047.09  4554.3 1043.85  4569.0 1045.69  4575.6 1043.52  4618.1 1042.09
  4627.5 1039.66  4633.4 1040.87  4685.4 1033.76  4722.0 1032.50  4743.2 1033.95
  4843.5 1031.98  4895.5 1033.99  4959.2 1031.60  4968.7 1033.42  4996.4 1030.03
  4997.5 1028.94  4997.7 1028.44  5001.5 1028.94  5081.5 1040.02  5204.0 1042.27
#Mann=7,-1,0
  4098.7    0.05       0  4486.9    0.12       0  4519.3    0.05       0
  4996.4    0.12       0  4997.5    0.07       0  5001.5    0.12       0
  5081.5    0.05       0
Bank Sta=4997.5,5001.5
Exp/Cntr=0.3,0.1

Type RM Length L Ch R = 1,500,0,0,0
BEGIN DESCRIPTION:
SANFERNANDO040 1.0
END DESCRIPTION:
XS GIS Cut Line= 3
      2803030.65     10240778.14      2802293.95     10241292.34
      2801955.72     10241403.10
#Sta/Elev= 30
  4101.6 1078.64  4180.8 1075.03  4229.8 1068.44  4302.8 1062.72  4351.9 1063.22
  4447.0 1048.91  4497.6 1045.40  4524.6 1041.32  4675.2 1034.81  4741.8 1030.30
  4754.0 1027.35  4783.7 1029.26  4819.5 1025.95  4849.1 1028.44  4876.2 1027.11
  4884.9 1028.57  4891.0 1026.92  4899.7 1028.98  4905.8 1027.22  4920.7 1031.74
  4941.6 1030.68  4994.3 1020.19  4994.6 1019.69  4998.3 1020.19  5008.7 1020.85
  5029.7 1029.17  5053.4 1031.53  5251.4 1040.74  5308.2 1043.10  5355.9 1042.28
#Mann=5,-1,0
  4101.6    0.05       0  4675.2    0.12       0  4994.3    0.07       0
  4998.3    0.12       0  5251.4    0.05       0
Bank Sta=4994.3,4998.3
Exp/Cntr=0.3,0.1

Chan Stop Cuts=-1