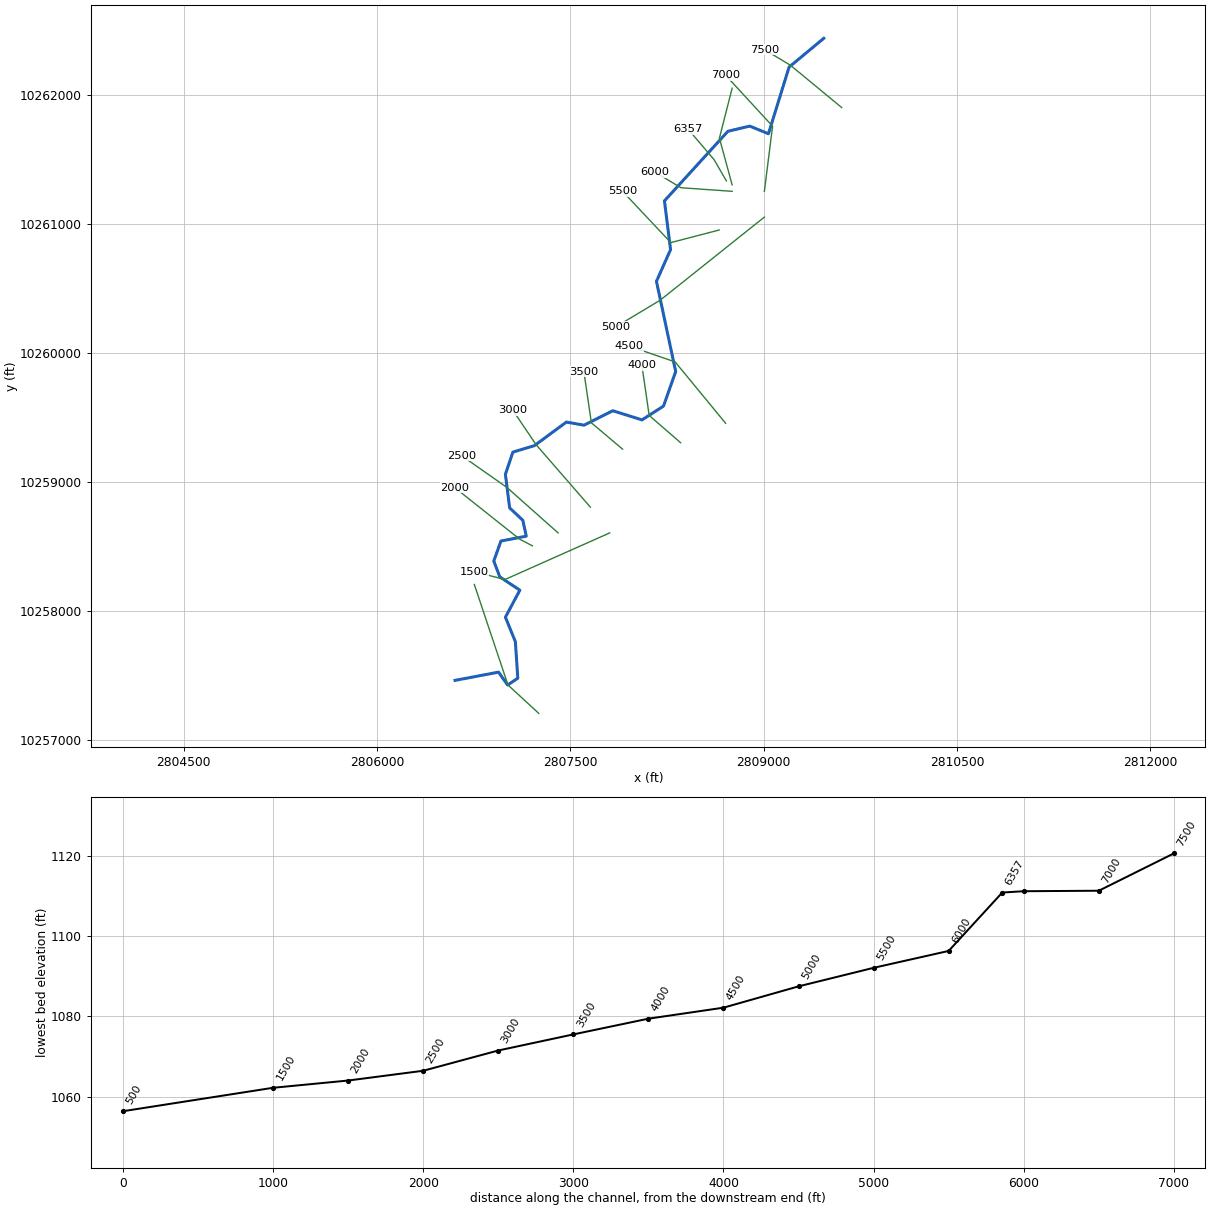
--- SANFERNANDO041.prj (project) ---

Proj Title=SANFERNANDO041 Base Level Engineering
Current Plan=p01
Default Exp/Contr=0.3,0.1
English Units
Geom File=g01
Flow File=f01
Plan File=p01
BEGIN DESCRIPTION:
SANFERNANDO041
END DESCRIPTION:

--- SANFERNANDO041.p01 (plan) ---

Plan Title=Multiple Run
Short Identifier=Multiple
Geom File=g01
Flow File=f01
Subcritical Flow
K Sum by GR= 0
Std Step Tol= 0.01
Critical Tol= 0.01
Num of Std Step Trials= 20
Max Error Tol= 0.3
Flow Tol Ratio= 0.001
Split Flow NTrial= 30
Split Flow Tol= 0.02
Split Flow Ratio= 0.02
Log Output Level= 0
Friction Slope Method= 1
Unsteady Friction Slope Method= 2
Unsteady Bridges Friction Slope Method= 1
Parabolic Critical Depth
Global Vel Dist=  1 , 1 , 1
Global Log Level= 0
CheckData=True
Encroach Param= -1, 0, 0, 0
BEGIN DESCRIPTION:
Multiple Run
END DESCRIPTION:

--- SANFERNANDO041.f01 (steady flow) ---

Flow Title=Multiple
Number of Profiles=7
Profile Names=10-year,25-year,50-year,1pct_min,100-year,1pct_plu,500-year
River Rch & RM= SANFERNANDO041,Reach-1,7500
     419     676    1009     668    1362    2779    1901
Boundary for River Rch & Prof#=SANFERNANDO041,Reach-1,1
Up Type=0
Dn Type=3
Dn Slope=0.005
Boundary for River Rch & Prof#=SANFERNANDO041,Reach-1,2
Up Type=0
Dn Type=3
Dn Slope=0.005
Boundary for River Rch & Prof#=SANFERNANDO041,Reach-1,3
Up Type=0
Dn Type=3
Dn Slope=0.005
Boundary for River Rch & Prof#=SANFERNANDO041,Reach-1,4
Up Type=0
Dn Type=3
Dn Slope=0.005
Boundary for River Rch & Prof#=SANFERNANDO041,Reach-1,5
Up Type=0
Dn Type=3
Dn Slope=0.005
Boundary for River Rch & Prof#=SANFERNANDO041,Reach-1,6
Up Type=0
Dn Type=3
Dn Slope=0.005
Boundary for River Rch & Prof#=SANFERNANDO041,Reach-1,7
Up Type=0
Dn Type=3
Dn Slope=0.005

--- SANFERNANDO041.g01 (geometry) ---

Geom Title=Existing Conditions

River Reach=SANFERNANDO041,Reach-1
Reach XY= 30
      2809466.75     10262440.00      2809197.50     10262217.00
      2809037.50     10261700.00      2808891.75     10261759.00
      2808723.00     10261719.00      2808230.50     10261179.00
      2808278.00     10260801.00      2808168.50     10260555.00
      2808317.75     10259855.00      2808223.25     10259587.00
      2808056.50     10259480.00      2807830.00     10259551.00
      2807606.75     10259439.00      2807469.75     10259463.00
      2807221.50     10259280.00      2807054.75     10259230.00
      2806996.75     10259058.00      2807029.75     10258797.00
      2807132.00     10258701.00      2807158.50     10258578.00
      2806962.00     10258540.00      2806906.50     10258385.00
      2806953.25     10258262.00      2807108.75     10258159.00
      2806996.75     10257949.00      2807074.00     10257760.00
      2807092.75     10257476.00      2807014.00     10257423.00
      2806943.50     10257523.00      2806606.00     10257459.00

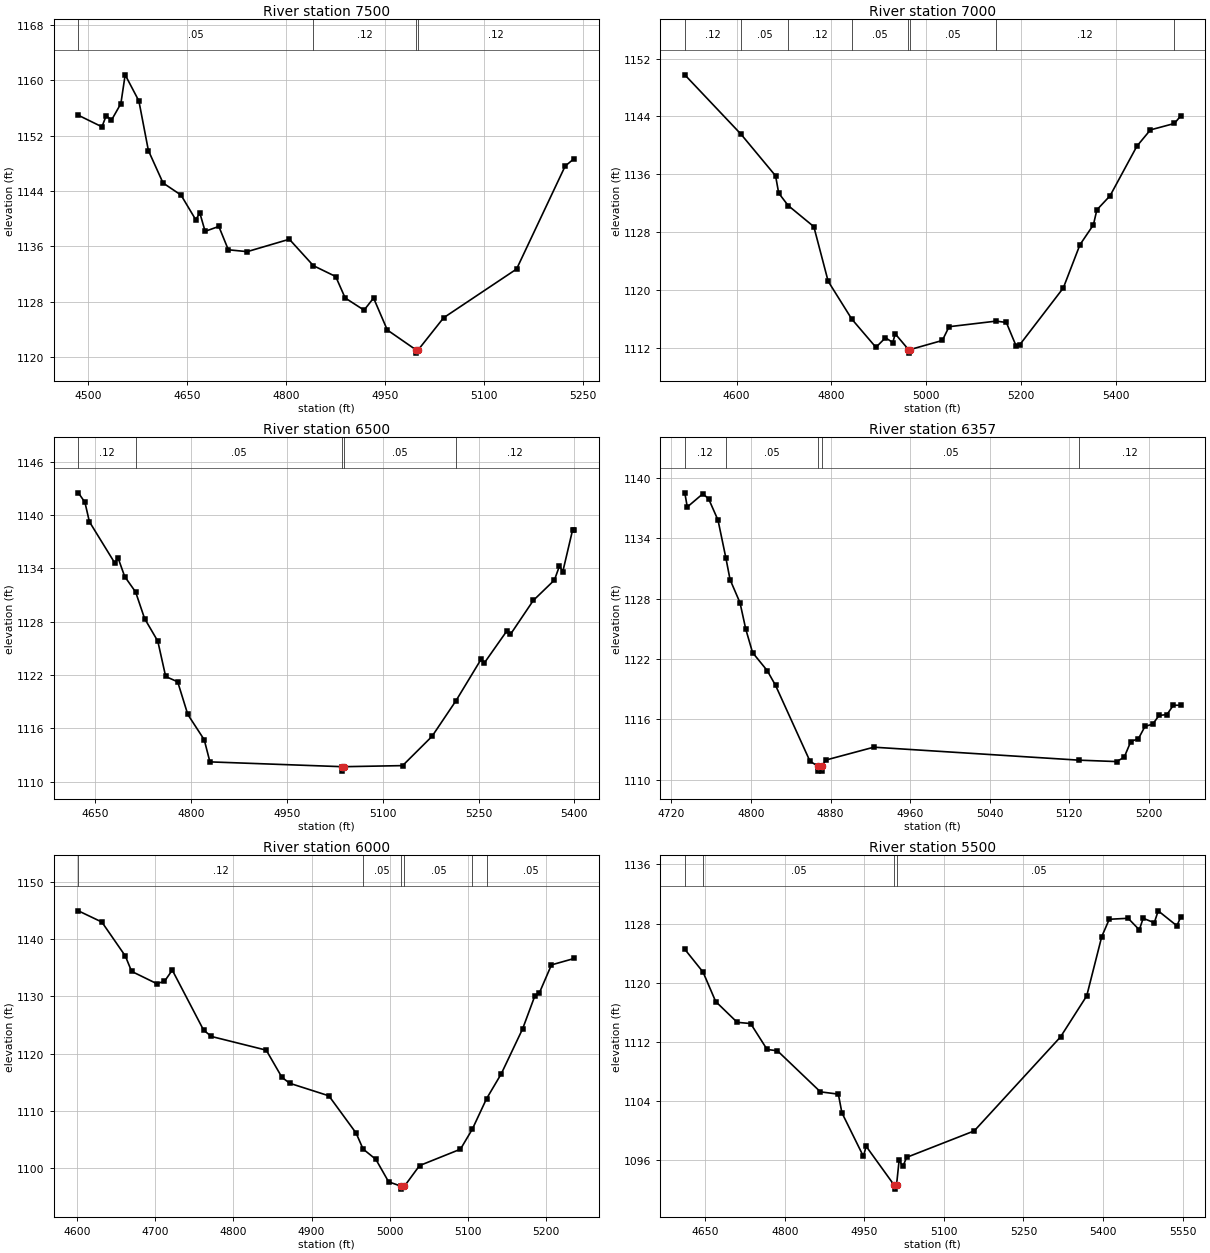
Type RM Length L Ch R = 1,7500,500,500,500
BEGIN DESCRIPTION:
SANFERNANDO041 14.0
END DESCRIPTION:
XS GIS Cut Line= 3
      2809605.68     10261903.11      2809208.38     10262230.80
      2809005.72     10262353.09
#Sta/Elev= 30
  4485.0 1154.93  4520.8 1153.26  4527.3 1154.88  4535.2 1154.21  4549.5 1156.61
  4556.0 1160.76  4576.8 1156.99  4591.2 1149.84  4613.4 1145.16  4640.7 1143.41
  4662.9 1139.87  4669.3 1140.80  4677.2 1138.18  4698.0 1138.89  4712.4 1135.52
  4741.0 1135.25  4804.9 1137.04  4841.3 1133.23  4875.2 1131.66  4889.5 1128.57
  4918.2 1126.81  4932.6 1128.56  4953.4 1123.95  4996.5 1121.11  4996.8 1120.61
  5000.5 1121.11  5038.8 1125.71  5149.4 1132.74  5223.1 1147.60  5236.7 1148.67
#Mann=4,-1,0
  4485.0    0.05       0  4841.3    0.12       0  4996.5    0.07       0
  5000.5    0.12       0
Bank Sta=4996.5,5000.5
Exp/Cntr=0.3,0.1

Type RM Length L Ch R = 1,7000,500,500,500
BEGIN DESCRIPTION:
SANFERNANDO041 13.0
END DESCRIPTION:
XS GIS Cut Line= 3
      2809005.68     10261253.09      2809069.44     10261758.18
      2808705.70     10262153.09
#Sta/Elev= 30
  4490.9 1149.75  4609.3 1141.56  4682.4 1135.80  4689.0 1133.41  4708.9 1131.70
  4763.1 1128.78  4793.3 1121.24  4843.2 1116.01  4894.1 1112.11  4914.3 1113.44
  4929.7 1112.77  4934.8 1113.98  4962.7 1111.81  4962.9 1111.31  4966.7 1111.81
  5034.2 1113.06  5048.4 1114.96  5147.5 1115.73  5169.2 1115.55  5190.1 1112.26
  5197.0 1112.42  5289.4 1120.31  5324.5 1126.28  5352.9 1129.03  5360.2 1131.10
  5388.1 1133.05  5444.8 1139.91  5473.1 1142.14  5523.7 1143.03  5536.9 1144.06
#Mann=8,-1,0
  4490.9    0.12       0  4609.3    0.05       0  4708.9    0.12       0
  4843.2    0.05       0  4962.7    0.03       0  4966.7    0.05       0
  5147.5    0.12       0  5523.7    0.05       0
Bank Sta=4962.7,4966.7
Exp/Cntr=0.3,0.1

Type RM Length L Ch R = 1,6500,143,143,143
BEGIN DESCRIPTION:
SANFERNANDO041 12.0
END DESCRIPTION:
XS GIS Cut Line= 3
      2808755.68     10261303.14      2808656.99     10261665.86
      2808755.68     10262053.08
#Sta/Elev= 30
  4624.1 1142.48  4634.4 1141.42  4641.4 1139.23  4681.1 1134.59  4686.3 1135.15
  4696.6 1133.07  4713.7 1131.33  4727.7 1128.35  4748.4 1125.80  4760.7 1121.83
  4779.5 1121.23  4795.3 1117.56  4821.0 1114.72  4829.9 1112.23  5036.4 1111.69
  5036.7 1111.19  5040.4 1111.69  5131.3 1111.81  5177.3 1115.10  5214.9 1119.12
  5253.9 1123.75  5259.1 1123.35  5294.8 1127.00  5300.0 1126.57  5335.7 1130.38
  5368.7 1132.67  5376.6 1134.25  5381.8 1133.61  5397.1 1138.29  5399.6 1138.29
#Mann=5,-1,0
  4624.1    0.12       0  4713.7    0.05       0  5036.4    0.03       0
  5040.4    0.05       0  5214.9    0.12       0
Bank Sta=5036.4,5040.4
Exp/Cntr=0.3,0.1

Type RM Length L Ch R = 1,6357,357,357,357
BEGIN DESCRIPTION:
Mapping XS 16533688
END DESCRIPTION:
XS GIS Cut Line= 3
      2808710.88     10261334.18      2808615.41     10261499.07
      2808415.77     10261733.43
#Sta/Elev= 30
  4733.5 1138.53  4736.0 1137.12  4751.7 1138.44  4757.5 1137.92  4766.9 1135.81
  4774.8 1132.05  4779.0 1129.90  4789.0 1127.60  4794.8 1124.97  4801.6 1122.65
  4816.3 1120.86  4824.7 1119.39  4859.4 1111.83  4867.4 1111.36  4867.6 1110.86
  4871.1 1110.86  4871.4 1111.36  4875.2 1111.96  4923.5 1113.24  5129.8 1111.95
  5167.5 1111.81  5175.2 1112.24  5181.8 1113.80  5189.5 1114.09  5196.1 1115.31
  5203.8 1115.53  5210.3 1116.40  5218.1 1116.48  5224.6 1117.41  5231.9 1117.41
#Mann=5,-1,0
  4733.5    0.12       0  4774.8    0.05       0  4867.4    0.03       0
  4871.4    0.05       0  5129.8    0.12       0
Bank Sta=4867.4,4871.4
Exp/Cntr=0.3,0.1

Type RM Length L Ch R = 1,6000,500,500,500
BEGIN DESCRIPTION:
SANFERNANDO041 11.0
END DESCRIPTION:
XS GIS Cut Line= 3
      2808755.71     10261253.11      2808358.09     10261281.13
      2808155.70     10261403.10
#Sta/Elev= 30
  4601.4 1144.95  4631.5 1142.99  4661.6 1137.05  4669.6 1134.37  4701.7 1132.23
  4711.7 1132.62  4721.7 1134.59  4761.8 1124.10  4771.8 1122.99  4842.0 1120.60
  4862.1 1115.85  4872.1 1114.81  4922.2 1112.62  4957.1 1106.10  4966.0 1103.32
  4982.4 1101.51  4998.7 1097.59  5014.9 1096.81  5015.2 1096.31  5018.9 1096.81
  5038.3 1100.42  5090.7 1103.29  5105.9 1106.79  5124.1 1112.11  5142.9 1116.45
  5170.3 1124.32  5185.8 1130.02  5191.7 1130.59  5207.2 1135.50  5236.3 1136.62
#Mann=6,-1,0
  4601.4    0.12       0  4966.0    0.05       0  5014.9    0.05       0
  5018.9    0.05       0  5105.9    0.12       0  5124.1    0.05       0
Bank Sta=5014.9,5018.9
Exp/Cntr=0.3,0.1

Type RM Length L Ch R = 1,5500,500,500,500
BEGIN DESCRIPTION:
SANFERNANDO041 10.0
END DESCRIPTION:
XS GIS Cut Line= 3
      2808655.73     10260953.12      2808279.96     10260855.29
      2807905.69     10261253.10
#Sta/Elev= 30
  4611.7 1124.52  4646.1 1121.44  4669.9 1117.46  4710.4 1114.65  4735.8 1114.48
  4766.8 1110.98  4786.3 1110.80  4867.3 1105.25  4901.1 1104.94  4907.8 1102.42
  4948.3 1096.53  4953.5 1097.89  5006.7 1092.60  5007.0 1092.10  5010.7 1092.60
  5015.6 1095.98  5022.9 1095.19  5029.7 1096.39  5157.2 1099.97  5319.8 1112.67
  5369.2 1118.22  5397.5 1126.23  5411.7 1128.58  5447.3 1128.71  5468.3 1127.15
  5475.6 1128.71  5496.6 1128.11  5503.9 1129.72  5539.1 1127.70  5546.2 1128.84
#Mann=4,-1,0
  4611.7    0.12       0  4646.1    0.05       0  5006.7    0.05       0
  5010.7    0.05       0
Bank Sta=5006.7,5010.7
Exp/Cntr=0.3,0.1

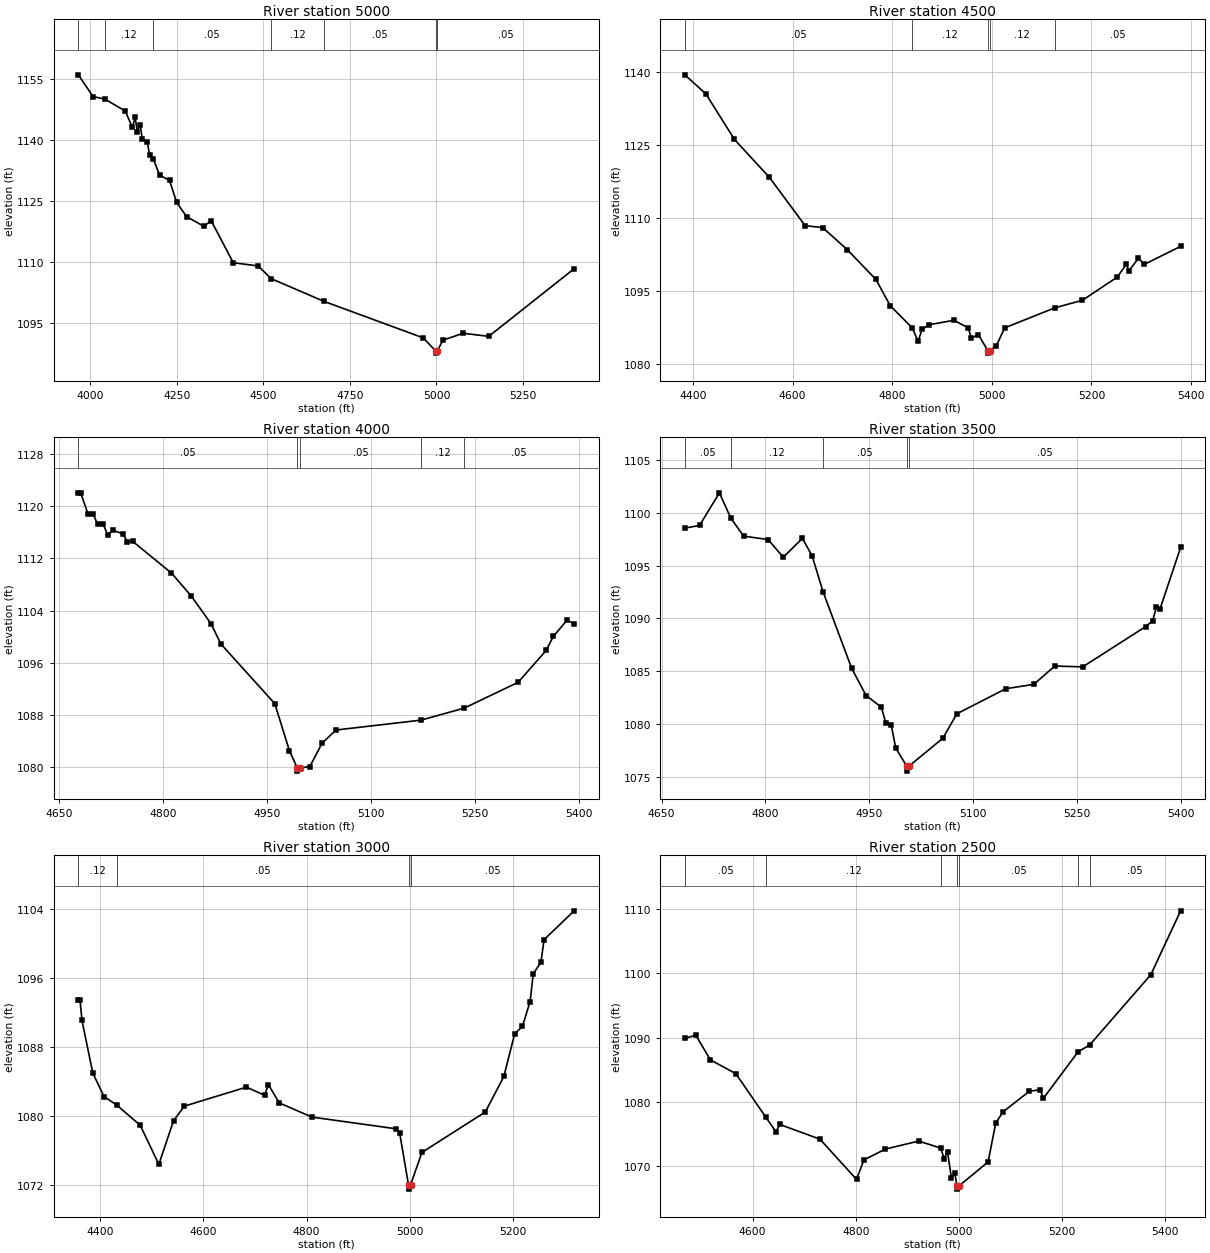
Type RM Length L Ch R = 1,5000,500,500,500
BEGIN DESCRIPTION:
SANFERNANDO041 9.0
END DESCRIPTION:
XS GIS Cut Line= 3
      2809005.66     10261053.09      2808196.72     10260407.94
      2807855.70     10260203.12
#Sta/Elev= 30
  3965.3 1156.07  4007.7 1150.72  4041.4 1150.10  4100.6 1147.18  4121.4 1143.13
  4129.4 1145.56  4135.8 1142.06  4143.8 1143.82  4150.2 1140.21  4164.6 1139.61
  4171.0 1136.31  4182.4 1135.24  4199.9 1131.36  4228.7 1130.06  4249.5 1124.61
  4278.3 1121.10  4328.0 1118.74  4349.0 1120.13  4413.0 1109.76  4484.9 1108.97
  4522.2 1105.84  4674.7 1100.25  4962.1 1091.23  4997.9 1087.98  4998.1 1087.48
  5001.9 1087.98  5018.9 1090.68  5077.2 1092.38  5151.0 1091.61  5397.8 1108.28
#Mann=7,-1,0
  3965.3    0.05       0  4041.4    0.12       0  4182.4    0.05       0
  4522.2    0.12       0  4674.7    0.05       0  4997.9    0.05       0
  5001.9    0.05       0
Bank Sta=4997.9,5001.9
Exp/Cntr=0.3,0.1

Type RM Length L Ch R = 1,4500,500,500,500
BEGIN DESCRIPTION:
SANFERNANDO041 8.0
END DESCRIPTION:
XS GIS Cut Line= 3
      2808705.67     10259453.13      2808313.94     10259929.30
      2807955.73     10260053.10
#Sta/Elev= 30
  4383.4 1139.34  4425.7 1135.43  4483.1 1126.06  4553.4 1118.26  4625.1 1108.35
  4660.3 1107.96  4709.8 1103.41  4767.2 1097.30  4795.9 1091.92  4840.3 1087.33
  4851.9 1084.56  4859.7 1087.06  4874.1 1088.01  4923.6 1088.91  4952.3 1087.39
  4958.8 1085.28  4973.1 1085.94  4991.9 1082.67  4992.2 1082.17  4995.9 1082.67
  5008.7 1083.64  5025.8 1087.36  5126.5 1091.48  5181.7 1093.02  5252.1 1097.81
  5269.9 1100.45  5275.2 1099.09  5294.4 1101.65  5306.4 1100.42  5379.0 1104.10
#Mann=5,-1,0
  4383.4    0.05       0  4840.3    0.12       0  4991.9    0.07       0
  4995.9    0.12       0  5126.5    0.05       0
Bank Sta=4991.9,4995.9
Exp/Cntr=0.3,0.1

Type RM Length L Ch R = 1,4000,500,500,500
BEGIN DESCRIPTION:
SANFERNANDO041 7.0
END DESCRIPTION:
XS GIS Cut Line= 3
      2808355.70     10259303.10      2808111.97     10259514.59
      2808055.68     10259903.13
#Sta/Elev= 30
  4677.3 1122.00  4680.6 1122.00  4691.1 1118.82  4698.7 1118.70  4705.3 1117.18
  4712.9 1117.26  4719.6 1115.57  4727.2 1116.25  4741.4 1115.75  4748.1 1114.55
  4755.7 1114.58  4811.7 1109.72  4840.2 1106.22  4868.7 1101.99  4882.9 1098.89
  4960.8 1089.74  4981.8 1082.56  4993.1 1079.93  4993.3 1079.43  4997.1 1079.93
  5011.3 1080.13  5028.8 1083.69  5049.0 1085.72  5171.7 1087.23  5234.0 1089.07
  5311.7 1093.01  5352.2 1097.89  5362.5 1100.03  5382.5 1102.54  5392.6 1101.94
#Mann=5,-1,0
  4677.3    0.05       0  4993.1    0.05       0  4997.1    0.05       0
  5171.7    0.12       0  5234.0    0.05       0
Bank Sta=4993.1,4997.1
Exp/Cntr=0.3,0.1

Type RM Length L Ch R = 1,3500,500,500,500
BEGIN DESCRIPTION:
SANFERNANDO041 6.0
END DESCRIPTION:
XS GIS Cut Line= 3
      2807905.65     10259253.14      2807663.72     10259457.21
      2807605.69     10259853.08
#Sta/Elev= 30
  4683.5 1098.56  4704.9 1098.82  4733.5 1101.91  4750.0 1099.51  4768.6 1097.80
  4803.8 1097.48  4825.8 1095.80  4853.5 1097.59  4867.5 1095.93  4883.4 1092.51
  4924.7 1085.26  4945.5 1082.68  4967.6 1081.58  4974.1 1080.03  4981.8 1079.90
  4988.4 1077.69  5004.0 1076.01  5004.2 1075.51  5008.0 1076.01  5056.5 1078.63
  5076.7 1080.95  5147.5 1083.33  5187.9 1083.74  5218.2 1085.48  5258.6 1085.40
  5349.6 1089.22  5359.7 1089.77  5365.2 1091.12  5370.3 1090.89  5400.1 1096.73
#Mann=5,-1,0
  4683.5    0.05       0  4750.0    0.12       0  4883.4    0.05       0
  5004.0    0.05       0  5008.0    0.05       0
Bank Sta=5004,5008
Exp/Cntr=0.3,0.1

Type RM Length L Ch R = 1,3000,500,500,500
BEGIN DESCRIPTION:
SANFERNANDO041 5.0
END DESCRIPTION:
XS GIS Cut Line= 3
      2807655.66     10258803.14      2807234.09     10259288.39
      2807055.70     10259553.09
#Sta/Elev= 30
  4357.2 1093.45  4360.5 1093.45  4364.3 1091.10  4385.2 1085.00  4407.0 1082.26
  4431.7 1081.27  4477.3 1078.92  4513.4 1074.38  4541.9 1079.44  4562.7 1081.14
  4683.3 1083.35  4718.5 1082.41  4726.1 1083.63  4747.0 1081.52  4810.6 1079.87
  4973.9 1078.51  4980.5 1078.07  4997.8 1072.00  4998.1 1071.50  5001.8 1072.00
  5023.9 1075.77  5146.8 1080.46  5182.8 1084.59  5203.8 1089.55  5218.8 1090.40
  5233.7 1093.30  5239.8 1096.53  5254.7 1097.85  5260.8 1100.49  5319.2 1103.84
#Mann=4,-1,0
  4357.2    0.12       0  4431.7    0.05       0  4997.8    0.05       0
  5001.8    0.05       0
Bank Sta=4997.8,5001.8
Exp/Cntr=0.3,0.1

Type RM Length L Ch R = 1,2500,500,500,500
BEGIN DESCRIPTION:
SANFERNANDO041 4.0
END DESCRIPTION:
XS GIS Cut Line= 3
      2807405.67     10258603.12      2807008.14     10258956.22
      2806655.71     10259203.09
#Sta/Elev= 30
  4468.3 1089.89  4489.6 1090.38  4518.0 1086.55  4567.4 1084.39  4625.9 1077.59
  4645.1 1075.37  4652.7 1076.50  4730.5 1074.22  4801.5 1067.96  4815.8 1070.99
  4857.6 1072.68  4922.0 1073.92  4965.0 1072.83  4971.3 1071.19  4978.0 1072.26
  4985.5 1068.25  4992.2 1068.94  4996.3 1066.95  4996.5 1066.45  5000.3 1066.95
  5056.8 1070.68  5071.6 1076.75  5086.4 1078.51  5137.0 1081.67  5157.9 1081.90
  5164.0 1080.56  5231.3 1087.80  5253.9 1088.87  5372.4 1099.78  5430.3 1109.72
#Mann=7,-1,0
  4468.3    0.05       0  4625.9    0.12       0  4965.0    0.05       0
  4996.3    0.03       0  5000.3    0.05       0  5231.3    0.12       0
  5253.9    0.05       0
Bank Sta=4996.3,5000.3
Exp/Cntr=0.3,0.1

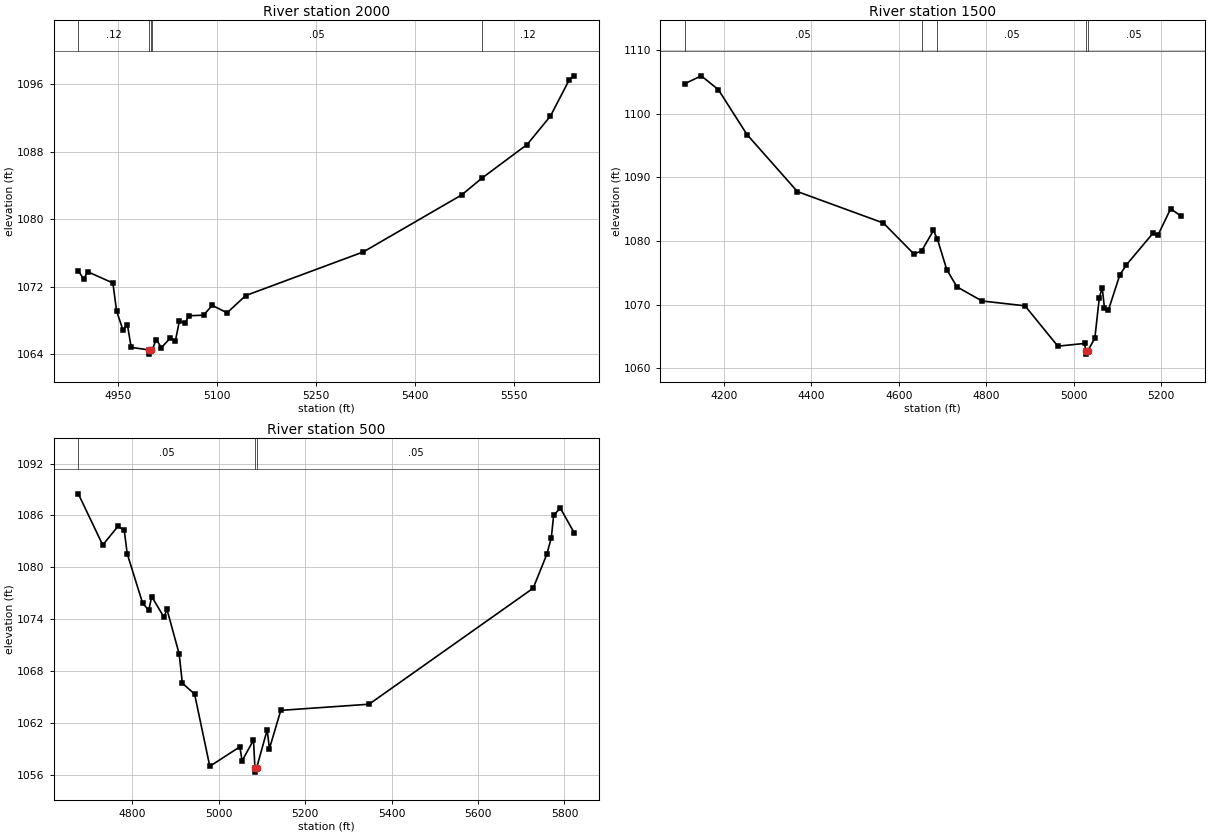
Type RM Length L Ch R = 1,2000,500,500,500
BEGIN DESCRIPTION:
SANFERNANDO041 3.0
END DESCRIPTION:
XS GIS Cut Line= 3
      2807205.72     10258503.09      2807107.80     10258554.29
      2806605.71     10258953.09
#Sta/Elev= 30
  4889.5 1073.88  4897.8 1072.87  4903.4 1073.78  4941.9 1072.44  4947.5 1069.13
  4957.2 1066.86  4964.0 1067.46  4969.6 1064.82  4996.4 1064.52  4996.6 1064.02
  5000.4 1064.52  5001.4 1064.52  5007.6 1065.75  5015.5 1064.78  5028.4 1065.89
  5036.5 1065.54  5042.8 1067.97  5050.9 1067.67  5057.3 1068.56  5079.3 1068.63
  5092.5 1069.79  5115.0 1068.91  5143.2 1070.95  5321.6 1076.12  5470.6 1082.86
  5501.7 1084.87  5569.9 1088.83  5605.2 1092.19  5634.0 1096.52  5641.2 1096.96
#Mann=5,-1,0
  4889.5    0.12       0  4996.4    0.07       0  5000.4    0.12       0
  5001.4    0.05       0  5501.7    0.12       0
Bank Sta=4996.4,5000.4
Exp/Cntr=0.3,0.1

Type RM Length L Ch R = 1,1500,1000,1000,1000
BEGIN DESCRIPTION:
SANFERNANDO041 2.0
END DESCRIPTION:
XS GIS Cut Line= 3
      2807805.71     10258603.12      2806992.61     10258241.24
      2806755.66     10258303.12
#Sta/Elev= 30
  4110.0 1104.70  4147.6 1105.94  4186.7 1103.78  4252.3 1096.72  4367.8 1087.75
  4564.6 1082.81  4634.4 1077.94  4652.0 1078.43  4679.2 1081.64  4688.4 1080.24
  4709.6 1075.49  4732.8 1072.79  4790.2 1070.56  4888.7 1069.80  4963.9 1063.46
  5024.9 1063.89  5028.1 1062.71  5028.3 1062.21  5032.1 1062.71  5048.5 1064.69
  5058.8 1071.08  5065.4 1072.64  5070.6 1069.46  5079.5 1069.11  5105.8 1074.68
  5120.8 1076.24  5181.6 1081.21  5193.2 1080.94  5222.1 1085.05  5244.9 1083.94
#Mann=5,-1,0
  4110.0    0.05       0  4652.0    0.12       0  4688.4    0.05       0
  5028.1    0.05       0  5032.1    0.05       0
Bank Sta=5028.1,5032.1
Exp/Cntr=0.3,0.1

Type RM Length L Ch R = 1,500,0,0,0
BEGIN DESCRIPTION:
SANFERNANDO041 1.0
END DESCRIPTION:
XS GIS Cut Line= 3
      2807255.65     10257203.14      2807016.68     10257423.25
      2806755.67     10258203.14
#Sta/Elev= 30
  4675.1 1088.50  4731.5 1082.59  4767.2 1084.77  4781.4 1084.27  4788.2 1081.58
  4823.9 1075.87  4838.1 1075.06  4844.9 1076.64  4873.3 1074.25  4880.1 1075.18
  4908.4 1070.02  4915.8 1066.64  4944.1 1065.38  4979.3 1057.04  5048.8 1059.29
  5054.1 1057.67  5080.4 1060.07  5083.7 1056.87  5083.9 1056.37  5087.7 1056.87
  5112.0 1061.24  5117.3 1059.09  5143.6 1063.50  5347.8 1064.21  5727.5 1077.60
  5759.1 1081.51  5769.6 1083.44  5775.0 1086.07  5790.7 1086.82  5822.4 1084.01
#Mann=3,-1,0
  4675.1    0.05       0  5083.7    0.05       0  5087.7    0.05       0
Bank Sta=5083.7,5087.7
Exp/Cntr=0.3,0.1

Chan Stop Cuts=-1