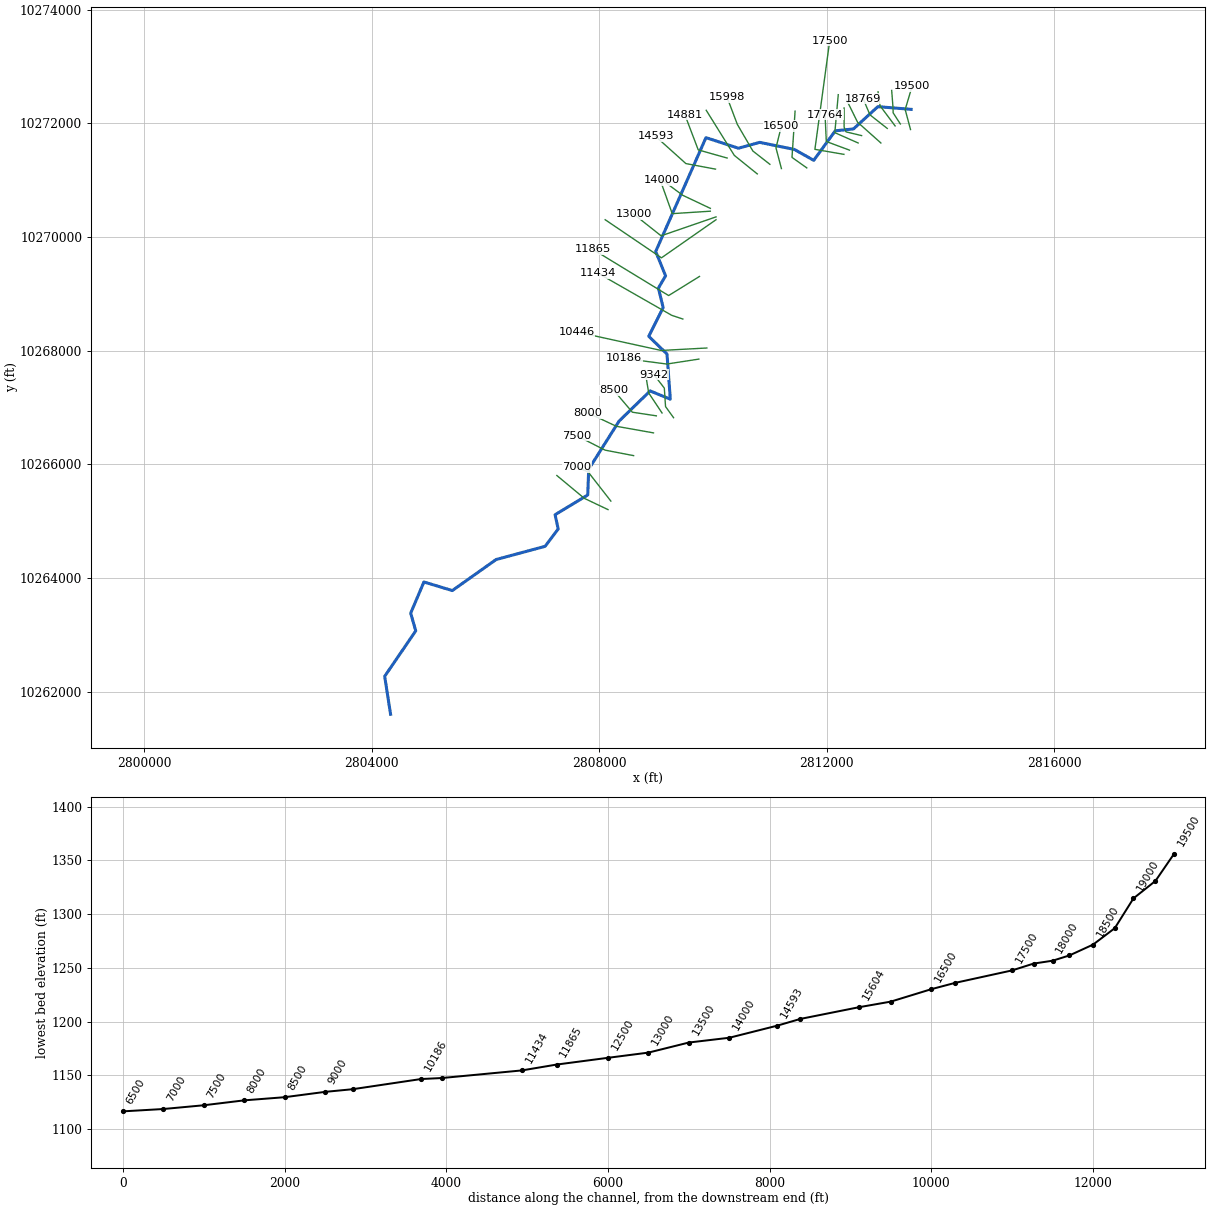
--- SANFERNANDO042.prj (project) ---

Proj Title=SANFERNANDO042 Base Level Engineering
Current Plan=p01
Default Exp/Contr=0.3,0.1
English Units
Geom File=g01
Flow File=f01
Plan File=p01
BEGIN DESCRIPTION:
SANFERNANDO042
END DESCRIPTION:

--- SANFERNANDO042.p01 (plan) ---

Plan Title=Multiple Run
Short Identifier=Multiple
Geom File=g01
Flow File=f01
Subcritical Flow
K Sum by GR= 0
Std Step Tol= 0.01
Critical Tol= 0.01
Num of Std Step Trials= 20
Max Error Tol= 0.3
Flow Tol Ratio= 0.001
Split Flow NTrial= 30
Split Flow Tol= 0.02
Split Flow Ratio= 0.02
Log Output Level= 0
Friction Slope Method= 1
Unsteady Friction Slope Method= 2
Unsteady Bridges Friction Slope Method= 1
Parabolic Critical Depth
Global Vel Dist=  1 , 1 , 1
Global Log Level= 0
CheckData=True
Encroach Param= -1, 0, 0, 0
BEGIN DESCRIPTION:
Multiple Run
END DESCRIPTION:

--- SANFERNANDO042.f01 (steady flow) ---

Flow Title=Multiple
Number of Profiles=7
Profile Names=10-year,25-year,50-year,1pct_min,100-year,1pct_plu,500-year
River Rch & RM= SANFERNANDO042,Reach-1,19500
     487     798    1417    1130    1970    3433    2829
River Rch & RM= SANFERNANDO042,Reach-1,7000
     803    1363    2337    1473    3285    7327    4675
Boundary for River Rch & Prof#=SANFERNANDO042,Reach-1,1
Up Type=0
Dn Type=3
Dn Slope=0.005
Boundary for River Rch & Prof#=SANFERNANDO042,Reach-1,2
Up Type=0
Dn Type=3
Dn Slope=0.005
Boundary for River Rch & Prof#=SANFERNANDO042,Reach-1,3
Up Type=0
Dn Type=3
Dn Slope=0.005
Boundary for River Rch & Prof#=SANFERNANDO042,Reach-1,4
Up Type=0
Dn Type=3
Dn Slope=0.005
Boundary for River Rch & Prof#=SANFERNANDO042,Reach-1,5
Up Type=0
Dn Type=3
Dn Slope=0.005
Boundary for River Rch & Prof#=SANFERNANDO042,Reach-1,6
Up Type=0
Dn Type=3
Dn Slope=0.005
Boundary for River Rch & Prof#=SANFERNANDO042,Reach-1,7
Up Type=0
Dn Type=3
Dn Slope=0.005

--- SANFERNANDO042.g01 (geometry) ---

Geom Title=Existing Conditions

River Reach=SANFERNANDO042,Reach-1
Reach XY= 30
      2813487.50     10272245.00      2812902.25     10272292.00
      2812474.00     10271901.00      2812153.50     10271867.00
      2811774.00     10271348.00      2811433.25     10271540.00
      2810823.50     10271664.00      2810450.25     10271561.00
      2809878.25     10271747.00      2808994.50     10269744.00
      2809168.25     10269316.00      2809042.25     10269101.00
      2809125.50     10268757.00      2808872.25     10268252.00
      2809193.25     10267940.00      2809251.50     10267146.00
      2808896.25     10267291.00      2808351.00     10266761.00
      2807815.75     10265914.00      2807799.00     10265461.00
      2807224.75     10265113.00      2807279.50     10264862.00
      2807048.50     10264557.00      2806187.50     10264325.00
      2805416.75     10263779.00      2804917.50     10263930.00
      2804684.75     10263382.00      2804773.50     10263070.00
      2804227.00     10262270.00      2804330.75     10261603.00

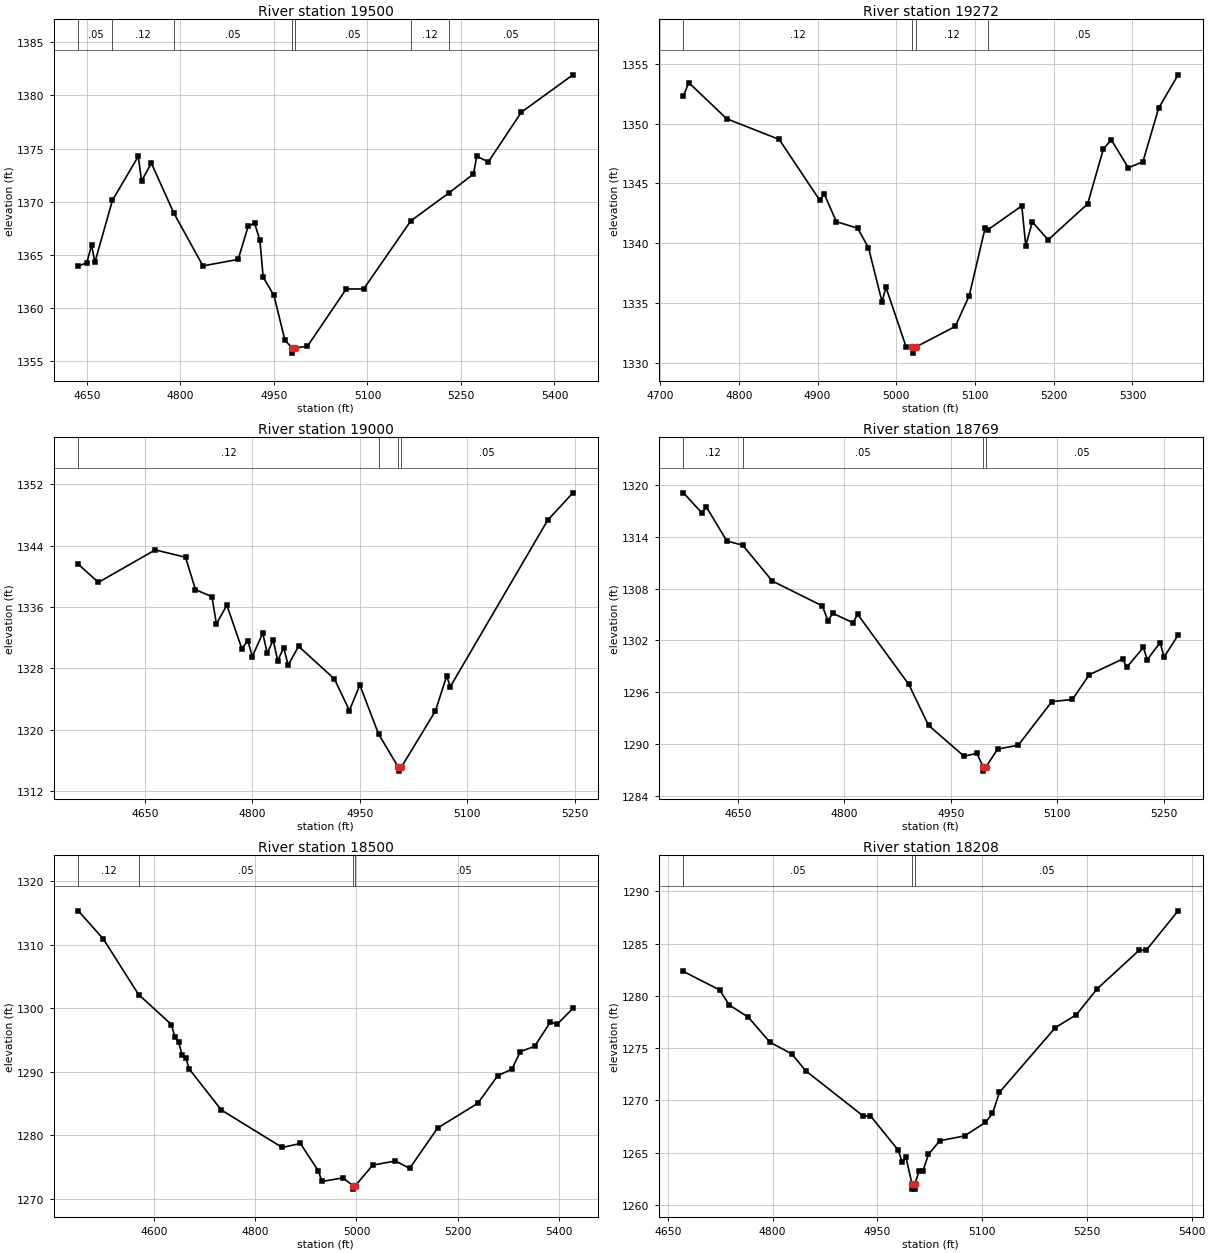
Type RM Length L Ch R = 1,19500,228,228,228
BEGIN DESCRIPTION:
SANFERNANDO042 39.0
END DESCRIPTION:
XS GIS Cut Line= 3
      2813476.86     10271889.88      2813382.83     10272241.42
      2813505.67     10272653.08
#Sta/Elev= 30
  4636.1 1363.96  4649.8 1364.28  4657.5 1365.95  4662.7 1364.31  4691.0 1370.16
  4732.4 1374.28  4737.6 1371.96  4753.3 1373.64  4789.4 1368.94  4836.1 1363.98
  4892.6 1364.59  4908.6 1367.70  4918.9 1368.00  4927.5 1366.38  4932.7 1362.92
  4950.0 1361.20  4967.6 1356.99  4979.0 1356.28  4979.3 1355.78  4983.0 1356.28
  5003.5 1356.41  5066.0 1361.81  5093.9 1361.81  5169.5 1368.21  5230.8 1370.84
  5270.1 1372.62  5275.3 1374.28  5294.0 1373.76  5346.8 1378.42  5429.6 1381.94
#Mann=7,-1,0
  4636.1    0.05       0  4691.0    0.12       0  4789.4    0.05       0
  4979.0    0.05       0  4983.0    0.05       0  5169.5    0.12       0
  5230.8    0.05       0
Bank Sta=4979,4983
Exp/Cntr=0.3,0.1

Type RM Length L Ch R = 1,19272,272,272,272
BEGIN DESCRIPTION:
Mapping XS 979785a2
END DESCRIPTION:
XS GIS Cut Line= 4
      2813297.46     10271987.39      2813171.62     10272182.67
      2813167.28     10272295.51      2813145.58     10272577.64
#Sta/Elev= 30
  4729.7 1352.32  4736.4 1353.43  4784.6 1350.41  4851.3 1348.68  4902.7 1343.61
  4908.7 1344.09  4923.9 1341.81  4950.9 1341.26  4964.7 1339.63  4981.9 1335.11
  4986.9 1336.32  5012.5 1331.34  5020.5 1331.32  5020.8 1330.82  5024.5 1331.32
  5074.9 1333.05  5092.6 1335.61  5112.7 1341.24  5116.8 1341.15  5159.4 1343.13
  5164.4 1339.81  5172.8 1341.78  5192.9 1340.29  5243.0 1343.29  5263.1 1347.89
  5273.1 1348.65  5294.7 1346.31  5313.2 1346.81  5333.3 1351.31  5357.9 1354.08
#Mann=4,-1,0
  4729.7    0.12       0  5020.5    0.07       0  5024.5    0.12       0
  5116.8    0.05       0
Bank Sta=5020.5,5024.5
Exp/Cntr=0.3,0.1

Type RM Length L Ch R = 1,19000,231,231,231
BEGIN DESCRIPTION:
SANFERNANDO042 38.0
END DESCRIPTION:
XS GIS Cut Line= 3
      2813205.67     10271953.12      2812940.95     10272308.08
      2812905.68     10272553.16
#Sta/Elev= 30
  4557.2 1341.59  4585.3 1339.22  4664.6 1343.46  4706.9 1342.50  4720.8 1338.27
  4743.8 1337.35  4750.0 1333.80  4764.6 1336.24  4785.5 1330.56  4793.8 1331.63
  4800.1 1329.54  4814.7 1332.59  4820.9 1329.98  4829.3 1331.70  4835.5 1328.99
  4843.9 1330.70  4850.1 1328.42  4864.7 1330.88  4914.8 1326.60  4935.6 1322.49
  4950.2 1325.82  4976.3 1319.42  5004.0 1315.08  5004.3 1314.58  5008.0 1315.08
  5055.6 1322.42  5071.4 1326.99  5076.5 1325.61  5212.3 1347.33  5247.6 1350.91
#Mann=4,-1,0
  4557.2    0.12       0  4976.3    0.05       0  5004.0    0.05       0
  5008.0    0.05       0
Bank Sta=5004,5008
Exp/Cntr=0.3,0.1

Type RM Length L Ch R = 1,18769,269,269,269
BEGIN DESCRIPTION:
Mapping XS 20170e0f
END DESCRIPTION:
XS GIS Cut Line= 3
      2813067.42     10271909.25      2812763.63     10272147.94
      2812642.11     10272434.39
#Sta/Elev= 30
  4572.9 1319.09  4598.8 1316.77  4605.2 1317.46  4634.1 1313.51  4656.3 1313.04
  4698.2 1308.88  4768.8 1306.00  4776.8 1304.25  4783.2 1305.15  4812.1 1304.06
  4818.5 1305.04  4890.7 1296.91  4918.5 1292.18  4968.5 1288.61  4986.6 1288.93
  4995.6 1287.38  4995.9 1286.88  4999.6 1287.38  5015.9 1289.43  5045.0 1289.88
  5092.3 1294.92  5121.4 1295.18  5145.1 1298.03  5192.4 1299.86  5197.8 1298.89
  5221.5 1301.19  5226.9 1299.78  5245.1 1301.76  5250.6 1300.08  5270.4 1302.62
#Mann=4,-1,0
  4572.9    0.12       0  4656.3    0.05       0  4995.6    0.05       0
  4999.6    0.05       0
Bank Sta=4995.6,4999.6
Exp/Cntr=0.3,0.1

Type RM Length L Ch R = 1,18500,292,292,292
BEGIN DESCRIPTION:
SANFERNANDO042 37.0
END DESCRIPTION:
XS GIS Cut Line= 3
      2812955.65     10271653.14      2812544.93     10272019.24
      2812355.68     10272403.13
#Sta/Elev= 30
  4449.8 1315.33  4499.5 1310.89  4569.0 1302.17  4634.1 1297.44  4640.8 1295.43
  4648.3 1294.75  4655.0 1292.62  4662.5 1292.19  4669.2 1290.45  4732.8 1284.00
  4853.2 1278.11  4889.1 1278.74  4924.2 1274.46  4931.8 1272.77  4973.6 1273.33
  4993.3 1272.06  4993.5 1271.56  4997.3 1272.06  5032.2 1275.34  5077.1 1275.99
  5105.1 1274.82  5160.4 1281.17  5239.9 1285.06  5279.2 1289.39  5307.3 1290.43
  5324.1 1293.20  5352.2 1294.00  5383.4 1297.84  5397.1 1297.51  5428.0 1299.99
#Mann=4,-1,0
  4449.8    0.12       0  4569.0    0.05       0  4993.3    0.03       0
  4997.3    0.05       0
Bank Sta=4993.3,4997.3
Exp/Cntr=0.3,0.1

Type RM Length L Ch R = 1,18208,208,208,208
BEGIN DESCRIPTION:
Mapping XS 9af6f7f9
END DESCRIPTION:
XS GIS Cut Line= 4
      2812616.07     10271783.36      2812342.62     10271848.46
      2812307.90     10271935.27      2812307.90     10272268.79
#Sta/Elev= 30
  4672.5 1282.33  4724.3 1280.56  4738.0 1279.13  4765.4 1277.95  4796.3 1275.56
  4827.4 1274.45  4847.7 1272.82  4929.9 1268.50  4940.2 1268.52  4980.1 1265.23
  4985.6 1264.07  4991.0 1264.56  4999.7 1262.01  4999.9 1261.51  5003.4 1261.51
  5003.7 1262.01  5009.9 1263.22  5015.3 1263.23  5023.2 1264.83  5039.5 1266.14
  5074.9 1266.60  5104.9 1267.90  5114.9 1268.75  5124.9 1270.77  5204.9 1276.96
  5234.9 1278.19  5264.9 1280.68  5324.9 1284.36  5334.9 1284.35  5380.6 1288.13
#Mann=3,-1,0
  4672.5    0.05       0  4999.7    0.05       0  5003.7    0.05       0
Bank Sta=4999.7,5003.7
Exp/Cntr=0.3,0.1

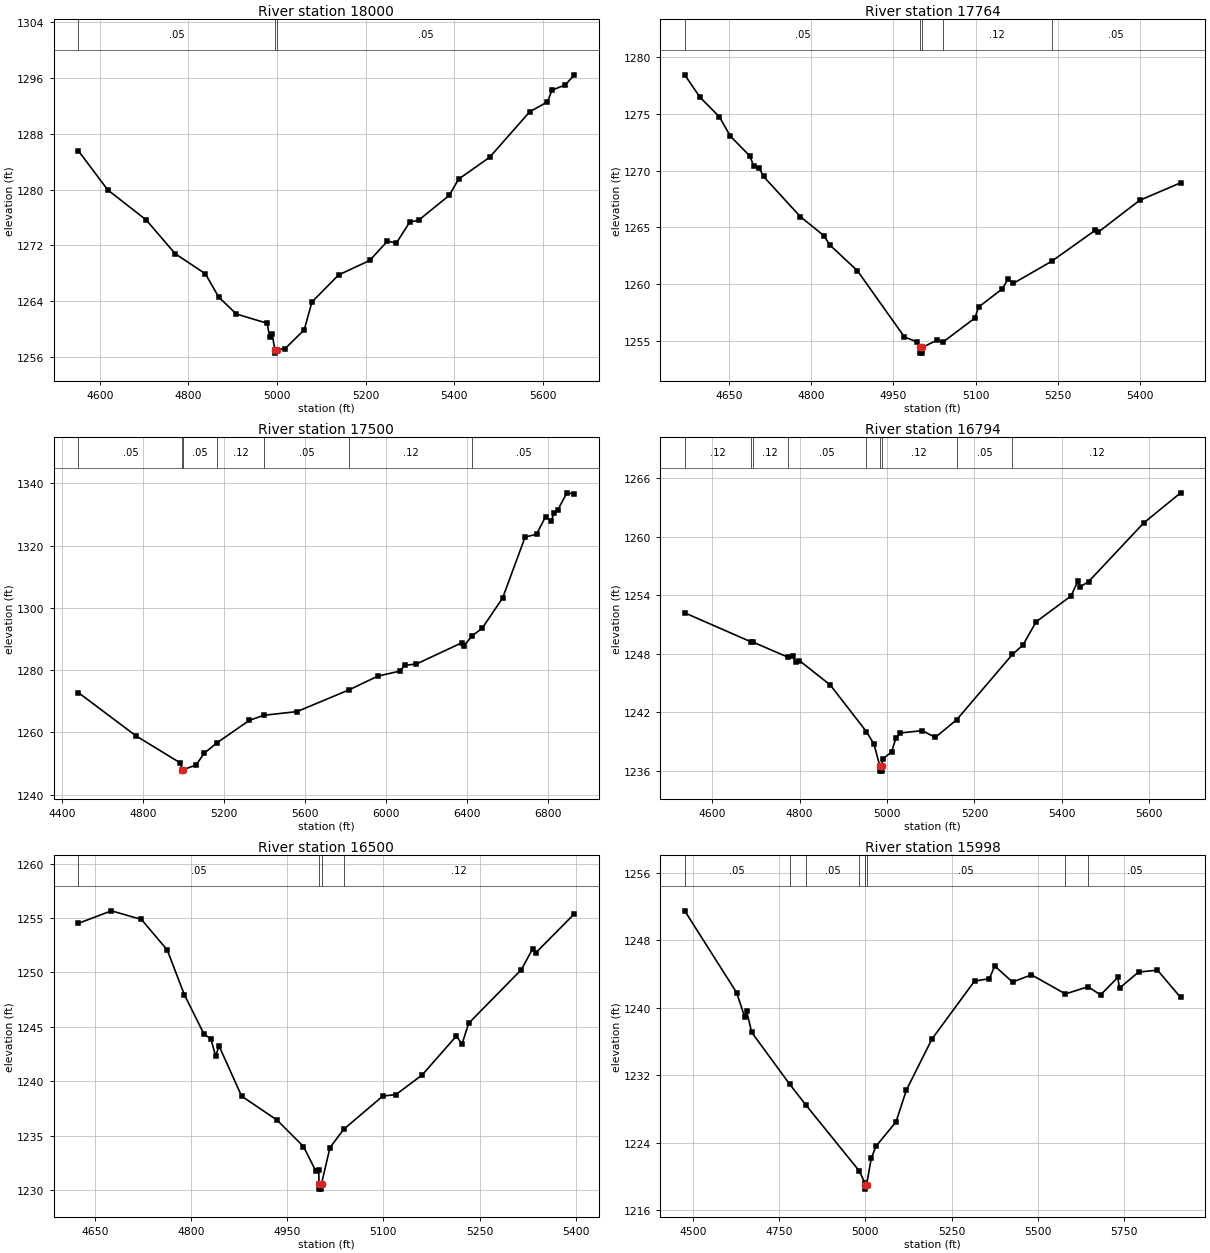
Type RM Length L Ch R = 1,18000,236,236,236
BEGIN DESCRIPTION:
SANFERNANDO042 36.0
END DESCRIPTION:
XS GIS Cut Line= 3
      2812555.68     10271653.11      2812145.35     10271834.65
      2812205.69     10272503.14
#Sta/Elev= 30
  4551.3 1285.56  4617.7 1279.95  4704.4 1275.66  4770.0 1270.82  4838.3 1267.94
  4868.4 1264.60  4908.2 1262.19  4977.8 1260.86  4983.5 1258.83  4989.0 1259.36
  4995.1 1257.09  4995.3 1256.59  4999.1 1257.09  5018.5 1257.25  5061.5 1259.93
  5078.8 1263.90  5139.0 1267.78  5209.3 1269.85  5249.5 1272.63  5269.5 1272.33
  5299.7 1275.35  5319.8 1275.61  5389.0 1279.17  5410.1 1281.49  5480.4 1284.63
  5570.8 1291.14  5610.7 1292.54  5621.0 1294.23  5651.1 1294.97  5671.2 1296.42
#Mann=3,-1,0
  4551.3    0.05       0  4995.1    0.03       0  4999.1    0.05       0
Bank Sta=4995.1,4999.1
Exp/Cntr=0.3,0.1

Type RM Length L Ch R = 1,17764,264,264,264
BEGIN DESCRIPTION:
Mapping XS 1379ab86
END DESCRIPTION:
XS GIS Cut Line= 3
      2812403.42     10271527.27      2811995.40     10271679.19
      2811973.70     10272147.90
#Sta/Elev= 30
  4569.5 1278.46  4597.2 1276.49  4632.8 1274.75  4652.5 1273.06  4688.2 1271.30
  4695.1 1270.45  4705.8 1270.20  4713.2 1269.49  4780.5 1265.94  4823.2 1264.27
  4834.5 1263.43  4884.5 1261.17  4970.2 1255.33  4993.9 1254.87  4998.5 1254.40
  4998.8 1253.90  5002.3 1253.90  5002.5 1254.40  5028.8 1255.02  5040.8 1254.88
  5098.9 1257.00  5105.4 1257.96  5149.0 1259.58  5159.0 1260.41  5169.0 1260.06
  5238.7 1262.00  5318.6 1264.75  5323.6 1264.57  5399.2 1267.38  5474.1 1268.93
#Mann=5,-1,0
  4569.5    0.05       0  4998.5    0.03       0  5002.5    0.05       0
  5040.8    0.12       0  5238.7    0.05       0
Bank Sta=4998.5,5002.5
Exp/Cntr=0.3,0.1

Type RM Length L Ch R = 1,17500,706,706,706
BEGIN DESCRIPTION:
SANFERNANDO042 35.0
END DESCRIPTION:
XS GIS Cut Line= 3
      2812305.68     10271453.11      2811794.83     10271541.26
      2812055.69     10273453.14
#Sta/Elev= 30
  4481.6 1272.81  4765.7 1258.93  4982.7 1250.31  4995.0 1248.09  4995.3 1247.59
  4999.0 1248.09  5062.4 1249.51  5102.8 1253.33  5167.8 1256.76  5324.8 1263.85
  5396.4 1265.51  5561.6 1266.71  5819.2 1273.72  5960.7 1278.10  6071.7 1279.74
  6091.9 1281.55  6150.1 1281.96  6377.1 1288.87  6384.6 1287.86  6427.2 1291.09
  6475.4 1293.47  6576.3 1303.18  6687.3 1322.75  6743.7 1323.62  6788.3 1329.33
  6816.1 1327.73  6828.6 1330.33  6848.8 1331.47  6893.4 1336.93  6929.6 1336.55
#Mann=7,-1,0
  4481.6    0.05       0  4995.0    0.05       0  4999.0    0.05       0
  5167.8    0.12       0  5396.4    0.05       0  5819.2    0.12       0
  6427.2    0.05       0
Bank Sta=4995,4999
Exp/Cntr=0.3,0.1

Type RM Length L Ch R = 1,16794,294,294,294
BEGIN DESCRIPTION:
Mapping XS 3b166ec3
END DESCRIPTION:
XS GIS Cut Line= 3
      2811652.43     10271214.85      2811392.05     10271399.28
      2811446.30     10272213.09
#Sta/Elev= 30
  4537.1 1252.19  4688.2 1249.23  4693.3 1249.19  4772.7 1247.66  4784.6 1247.79
  4790.8 1247.11  4799.4 1247.30  4870.0 1244.80  4952.8 1240.02  4970.3 1238.72
  4983.6 1236.47  4983.9 1235.97  4987.4 1235.97  4987.6 1236.47  4990.7 1237.25
  5010.4 1237.92  5020.4 1239.38  5030.4 1239.88  5080.5 1240.12  5110.6 1239.43
  5159.7 1241.25  5286.9 1247.93  5311.0 1248.89  5341.1 1251.27  5421.3 1253.93
  5436.6 1255.45  5441.7 1254.84  5461.4 1255.40  5587.0 1261.39  5671.8 1264.49
#Mann=9,-1,0
  4537.1    0.12       0  4688.2    0.05       0  4693.3    0.12       0
  4772.7    0.05       0  4952.8    0.12       0  4983.6    0.07       0
  4987.6    0.12       0  5159.7    0.05       0  5286.9    0.12       0
Bank Sta=4983.6,4987.6
Exp/Cntr=0.3,0.1

Type RM Length L Ch R = 1,16500,502,502,502
BEGIN DESCRIPTION:
SANFERNANDO042 33.0
END DESCRIPTION:
XS GIS Cut Line= 3
      2811205.67     10271203.15      2811110.30     10271566.96
      2811205.69     10271953.15
#Sta/Elev= 30
  4623.9 1254.51  4675.5 1255.66  4722.3 1254.87  4762.6 1252.07  4789.3 1247.97
  4820.3 1244.31  4830.6 1243.93  4838.3 1242.31  4843.4 1243.27  4878.7 1238.65
  4934.0 1236.45  4975.3 1234.02  4994.7 1231.75  4999.2 1231.86  4999.4 1230.61
  4999.6 1230.11  5003.1 1230.11  5003.4 1230.61  5016.6 1233.92  5038.0 1235.60
  5099.0 1238.65  5119.6 1238.79  5160.8 1240.61  5213.8 1244.16  5222.7 1243.43
  5233.0 1245.33  5315.4 1250.27  5333.0 1252.18  5338.2 1251.83  5397.8 1255.37
#Mann=4,-1,0
  4623.9    0.05       0  4999.4    0.05       0  5003.4    0.05       0
  5038.0    0.12       0
Bank Sta=4999.4,5003.4
Exp/Cntr=0.3,0.1

Type RM Length L Ch R = 1,15998,394,394,394
BEGIN DESCRIPTION:
Mapping XS 2d7c3bab
END DESCRIPTION:
XS GIS Cut Line= 4
      2811002.93     10271277.92      2810703.41     10271512.32
      2810429.98     10271981.07      2810247.69     10272462.84
#Sta/Elev= 30
  4476.2 1251.50  4627.0 1241.78  4649.6 1238.96  4655.9 1239.58  4670.4 1237.10
  4780.9 1230.93  4827.1 1228.51  4982.2 1220.68  4998.6 1219.25  4999.5 1219.02
  4999.8 1218.52  5003.5 1219.02  5017.2 1222.19  5031.1 1223.62  5089.0 1226.49
  5118.9 1230.25  5193.2 1236.31  5316.6 1243.17  5359.6 1243.46  5375.3 1244.96
  5426.8 1243.06  5481.8 1243.92  5580.1 1241.65  5645.7 1242.50  5682.2 1241.54
  5731.9 1243.60  5737.2 1242.34  5792.2 1244.24  5847.2 1244.47  5914.3 1241.23
#Mann=9,-1,0
  4476.2    0.05       0  4780.9    0.12       0  4827.1    0.05       0
  4982.2    0.12       0  4998.6    0.05       0  4999.5    0.03       0
  5003.5    0.05       0  5580.1    0.12       0  5645.7    0.05       0
Bank Sta=4999.5,5003.5
Exp/Cntr=0.3,0.1

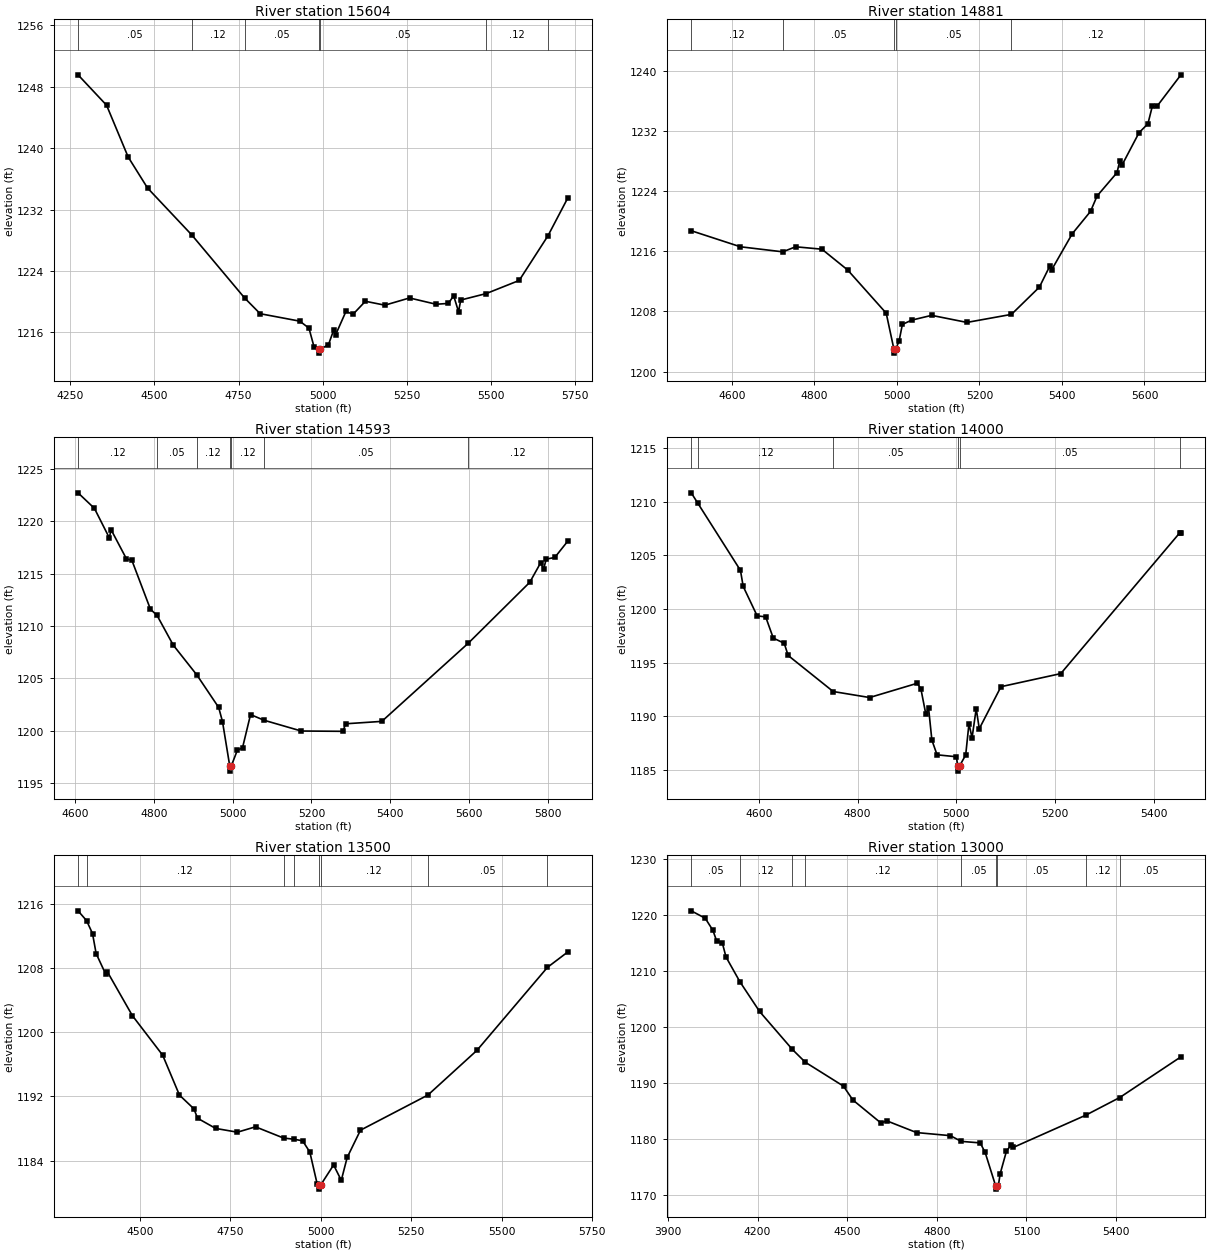
Type RM Length L Ch R = 1,15604,723,723,723
BEGIN DESCRIPTION:
Mapping XS 994cdea1
END DESCRIPTION:
XS GIS Cut Line= 3
      2810781.50     10271108.71      2810377.89     10271434.20
      2809883.20     10272228.32
#Sta/Elev= 30
  4273.2 1249.53  4358.0 1245.57  4422.0 1238.84  4479.6 1234.80  4611.2 1228.68
  4767.6 1220.50  4814.0 1218.44  4931.8 1217.47  4958.9 1216.56  4974.3 1214.08
  4987.6 1213.81  4987.9 1213.31  4991.6 1213.81  5016.8 1214.40  5032.1 1216.28
  5038.0 1215.69  5068.7 1218.73  5089.9 1218.37  5126.5 1220.06  5184.3 1219.55
  5257.5 1220.49  5336.6 1219.67  5373.2 1219.78  5388.5 1220.79  5403.1 1218.70
  5409.7 1220.22  5485.2 1221.06  5583.2 1222.77  5668.6 1228.58  5727.3 1233.49
#Mann=7,-1,0
  4273.2    0.05       0  4611.2    0.12       0  4767.6    0.05       0
  4987.6    0.03       0  4991.6    0.05       0  5485.2    0.12       0
  5668.6    0.05       0
Bank Sta=4987.6,4991.6
Exp/Cntr=0.3,0.1

Type RM Length L Ch R = 1,14881,288,288,288
BEGIN DESCRIPTION:
Mapping XS bde87ef7
END DESCRIPTION:
XS GIS Cut Line= 3
      2810250.60     10271388.40      2809742.80     10271531.62
      2809508.42     10272147.95
#Sta/Elev= 30
  4501.4 1218.75  4620.8 1216.61  4723.2 1215.94  4754.4 1216.61  4818.2 1216.29
  4880.6 1213.52  4974.0 1207.77  4992.8 1202.95  4993.1 1202.45  4996.8 1202.95
  5005.2 1204.06  5013.2 1206.27  5035.5 1206.84  5084.1 1207.48  5169.7 1206.54
  5277.6 1207.61  5345.3 1211.24  5370.1 1213.99  5375.4 1213.58  5425.0 1218.35
  5469.2 1221.32  5485.2 1223.38  5533.4 1226.48  5540.1 1228.01  5545.4 1227.47
  5586.9 1231.81  5608.3 1232.98  5619.0 1235.32  5630.4 1235.32  5688.4 1239.51
#Mann=5,-1,0
  4501.4    0.12       0  4723.2    0.05       0  4992.8    0.03       0
  4996.8    0.05       0  5277.6    0.12       0
Bank Sta=4992.8,4996.8
Exp/Cntr=0.3,0.1

Type RM Length L Ch R = 1,14593,593,593,593
BEGIN DESCRIPTION:
Mapping XS 03cc7ba0
END DESCRIPTION:
XS GIS Cut Line= 3
      2810046.54     10271193.12      2809525.73     10271290.77
      2808994.09     10271768.16
#Sta/Elev= 30
  4606.8 1222.72  4648.4 1221.24  4686.1 1218.44  4691.1 1219.18  4729.8 1216.42
  4743.7 1216.27  4790.8 1211.61  4807.7 1211.01  4848.8 1208.18  4909.0 1205.32
  4964.2 1202.23  4973.9 1200.88  4992.3 1196.65  4992.5 1196.15  4996.3 1196.65
  5011.6 1198.14  5024.8 1198.38  5045.2 1201.55  5079.4 1201.01  5174.0 1199.98
  5280.1 1199.95  5286.8 1200.67  5378.8 1200.90  5598.4 1208.36  5754.8 1214.18
  5782.4 1216.04  5789.9 1215.45  5796.6 1216.39  5818.3 1216.55  5851.2 1218.10
#Mann=7,-1,0
  4606.8    0.12       0  4807.7    0.05       0  4909.0    0.12       0
  4992.3    0.07       0  4996.3    0.12       0  5079.4    0.05       0
  5598.4    0.12       0
Bank Sta=4992.3,4996.3
Exp/Cntr=0.3,0.1

Type RM Length L Ch R = 1,14000,500,500,500
BEGIN DESCRIPTION:
SANFERNANDO042 28.0
END DESCRIPTION:
XS GIS Cut Line= 3
      2809955.69     10270503.11      2809470.82     10270732.73
      2809105.72     10271003.09
#Sta/Elev= 30
  4463.5 1210.84  4476.7 1209.88  4563.1 1203.61  4568.6 1202.12  4596.9 1199.37
  4614.1 1199.28  4629.5 1197.30  4651.6 1196.82  4659.6 1195.68  4750.7 1192.32
  4824.4 1191.76  4920.9 1193.09  4928.2 1192.56  4938.1 1190.22  4943.7 1190.78
  4950.4 1187.79  4960.9 1186.42  5000.0 1186.24  5002.6 1185.40  5002.9 1184.90
  5006.6 1185.40  5018.8 1186.40  5025.4 1189.31  5031.7 1188.01  5040.1 1190.72
  5046.3 1188.85  5090.2 1192.77  5211.2 1193.99  5451.9 1207.11  5454.3 1207.11
#Mann=6,-1,0
  4463.5    0.05       0  4476.7    0.12       0  4750.7    0.05       0
  5002.6    0.05       0  5006.6    0.05       0  5451.9    0.12       0
Bank Sta=5002.6,5006.6
Exp/Cntr=0.3,0.1

Type RM Length L Ch R = 1,13500,500,500,500
BEGIN DESCRIPTION:
SANFERNANDO042 27.0
END DESCRIPTION:
XS GIS Cut Line= 3
      2809955.66     10270453.11      2809285.26     10270409.86
      2809055.68     10271053.12
#Sta/Elev= 30
  4328.2 1215.12  4351.7 1213.91  4368.3 1212.29  4378.3 1209.80  4404.6 1207.25
  4409.6 1207.51  4478.5 1202.07  4562.4 1197.14  4608.8 1192.17  4648.8 1190.46
  4658.9 1189.29  4709.0 1188.02  4769.1 1187.55  4819.2 1188.22  4896.9 1186.82
  4924.8 1186.68  4949.5 1186.48  4969.5 1185.08  4989.6 1181.15  4995.3 1180.96
  4995.5 1180.46  4999.3 1180.96  5035.3 1183.47  5056.5 1181.55  5072.8 1184.40
  5109.6 1187.80  5296.3 1192.18  5431.8 1197.74  5626.9 1208.08  5683.0 1209.99
#Mann=8,-1,0
  4328.2    0.05       0  4351.7    0.12       0  4896.9    0.05       0
  4924.8    0.12       0  4995.3    0.07       0  4999.3    0.12       0
  5296.3    0.05       0  5626.9    0.12       0
Bank Sta=4995.3,4999.3
Exp/Cntr=0.3,0.1

Type RM Length L Ch R = 1,13000,500,500,500
BEGIN DESCRIPTION:
SANFERNANDO042 26.0
END DESCRIPTION:
XS GIS Cut Line= 3
      2810055.69     10270353.11      2809089.47     10270020.07
      2808605.66     10270403.13
#Sta/Elev= 30
  3978.0 1220.69  4024.8 1219.37  4050.7 1217.20  4062.6 1215.38  4081.9 1215.00
  4094.4 1212.46  4140.9 1208.05  4206.8 1202.75  4316.6 1195.98  4359.7 1193.71
  4487.7 1189.44  4518.9 1186.98  4612.6 1182.89  4633.1 1183.25  4732.1 1181.17
  4845.3 1180.62  4881.8 1179.60  4945.2 1179.33  4961.7 1177.64  4997.4 1171.59
  4997.6 1171.09  5001.4 1171.59  5005.6 1171.59  5012.1 1173.84  5032.9 1177.81
  5047.3 1178.89  5055.4 1178.51  5297.9 1184.25  5412.4 1187.42  5617.1 1194.67
#Mann=9,-1,0
  3978.0    0.05       0  4140.9    0.12       0  4316.6    0.05       0
  4359.7    0.12       0  4881.8    0.05       0  4997.4    0.05       0
  5001.4    0.05       0  5297.9    0.12       0  5412.4    0.05       0
Bank Sta=4997.4,5001.4
Exp/Cntr=0.3,0.1

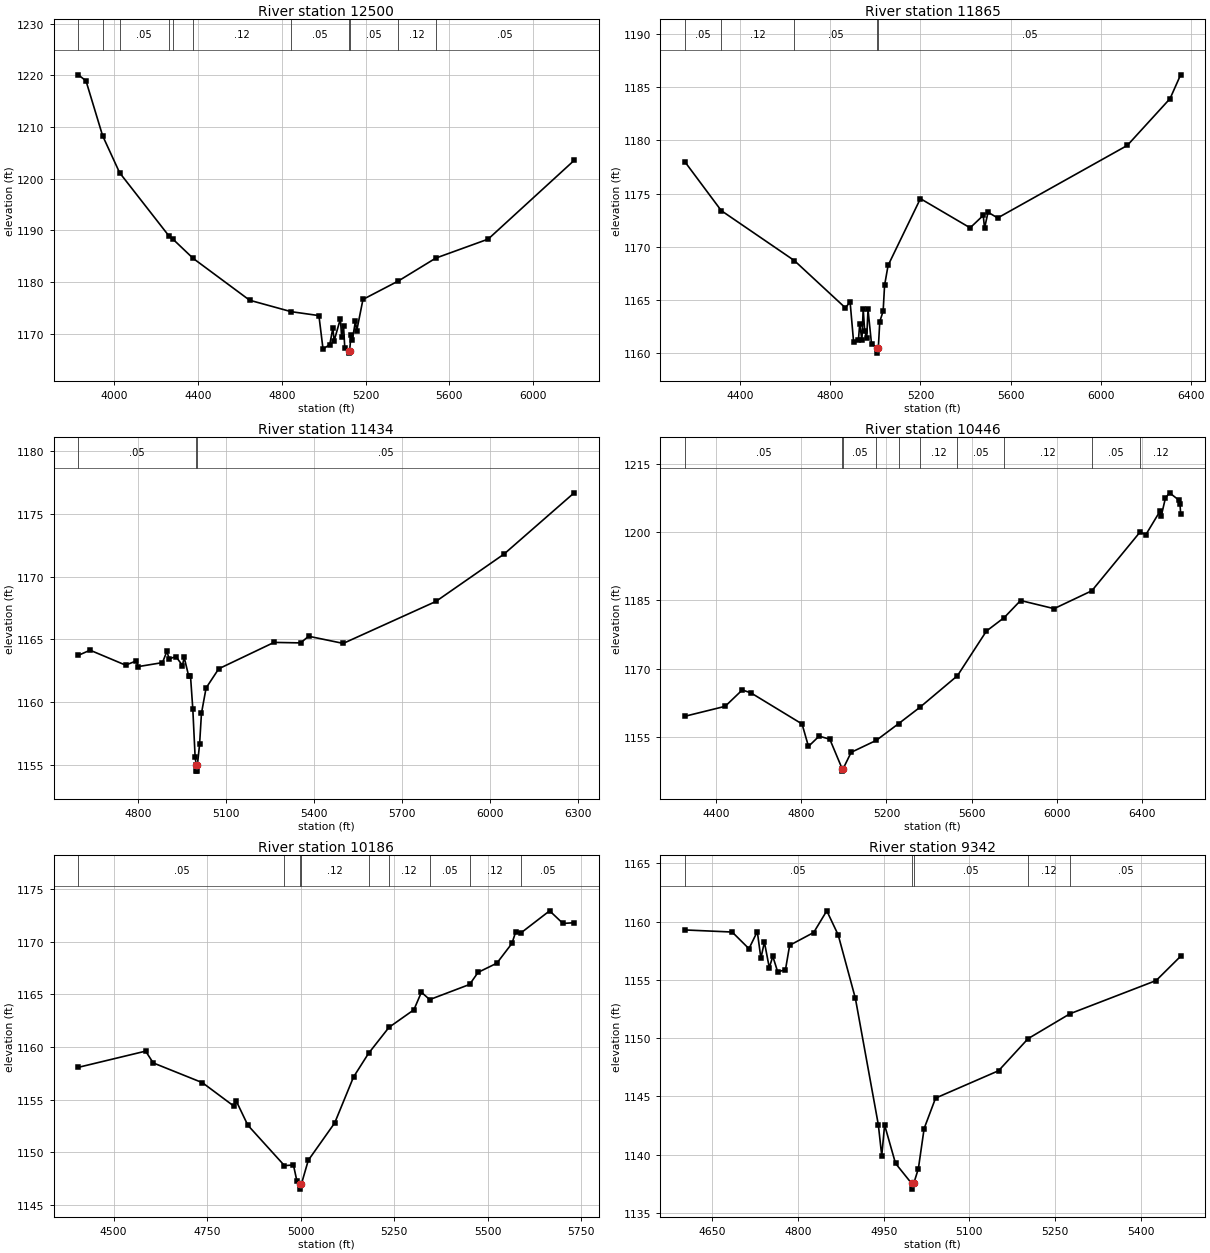
Type RM Length L Ch R = 1,12500,635,635,635
BEGIN DESCRIPTION:
SANFERNANDO042 25.0
END DESCRIPTION:
XS GIS Cut Line= 3
      2810055.67     10270303.10      2809095.49     10269632.63
      2808105.70     10270303.10
#Sta/Elev= 30
  3828.9 1220.08  3865.5 1218.91  3944.7 1208.31  4026.0 1201.14  4259.9 1188.99
  4281.3 1188.26  4376.8 1184.58  4646.6 1176.48  4844.6 1174.27  4977.2 1173.51
  4996.8 1167.05  5028.8 1167.88  5043.7 1171.09  5049.8 1168.62  5079.7 1172.89
  5085.7 1169.36  5094.6 1171.56  5100.7 1167.26  5119.7 1166.75  5119.9 1166.25
  5123.7 1166.75  5130.6 1169.68  5136.6 1168.78  5151.6 1172.46  5157.6 1170.56
  5187.5 1176.64  5356.2 1180.20  5535.0 1184.63  5784.9 1188.30  6195.5 1203.53
#Mann=11,-1,0
  3828.9    0.05       0  3944.7    0.12       0  4026.0    0.05       0
  4259.9    0.12       0  4281.3    0.05       0  4376.8    0.12       0
  4844.6    0.05       0  5119.7    0.03       0  5123.7    0.05       0
  5356.2    0.12       0  5535.0    0.05       0
Bank Sta=5119.7,5123.7
Exp/Cntr=0.3,0.1

Type RM Length L Ch R = 1,11865,431,431,431
BEGIN DESCRIPTION:
Mapping XS 4dcf70ae
END DESCRIPTION:
XS GIS Cut Line= 3
      2809764.47     10269305.11      2809221.91     10268968.72
      2807888.95     10269781.50
#Sta/Elev= 30
  4154.4 1178.00  4316.2 1173.39  4640.1 1168.69  4866.5 1164.24  4887.8 1164.78
  4903.2 1161.03  4924.6 1161.21  4930.4 1162.73  4940.0 1161.20  4945.9 1164.11
  4952.3 1162.06  4961.3 1161.38  4967.2 1164.08  4982.7 1160.84  5008.9 1160.47
  5009.1 1159.97  5012.9 1160.47  5019.4 1162.94  5034.3 1163.93  5040.7 1166.36
  5056.2 1168.23  5199.6 1174.52  5420.2 1171.77  5478.3 1172.94  5484.2 1171.74
  5499.6 1173.24  5542.3 1172.70  6117.4 1179.53  6307.1 1183.94  6354.0 1186.18
#Mann=5,-1,0
  4154.4    0.05       0  4316.2    0.12       0  4640.1    0.05       0
  5008.9    0.03       0  5012.9    0.05       0
Bank Sta=5008.9,5012.9
Exp/Cntr=0.3,0.1

Type RM Length L Ch R = 1,11434,988,988,988
BEGIN DESCRIPTION:
Mapping XS 91f57b77
END DESCRIPTION:
XS GIS Cut Line= 3
      2809471.46     10268556.40      2809276.16     10268621.50
      2807986.00     10269358.74
#Sta/Elev= 30
  4596.5 1163.73  4636.5 1164.14  4757.7 1162.95  4794.6 1163.29  4800.0 1162.83
  4883.5 1163.15  4898.6 1164.04  4906.6 1163.45  4929.6 1163.63  4951.8 1162.92
  4957.6 1163.57  4973.4 1162.05  4979.2 1162.10  4987.2 1159.42  4995.0 1155.62
  4998.8 1155.01  4999.0 1154.51  5002.5 1154.51  5002.8 1155.01  5010.2 1156.64
  5016.6 1159.11  5032.4 1161.13  5075.6 1162.66  5264.2 1164.76  5354.9 1164.72
  5382.3 1165.25  5500.3 1164.68  5816.4 1168.02  6048.9 1171.79  6288.3 1176.67
#Mann=3,-1,0
  4596.5    0.05       0  4998.8    0.05       0  5002.8    0.05       0
Bank Sta=4998.8,5002.8
Exp/Cntr=0.3,0.1

Type RM Length L Ch R = 1,10446,260,260,260
BEGIN DESCRIPTION:
Mapping XS 28a8f861
END DESCRIPTION:
XS GIS Cut Line= 3
      2809894.70     10268046.42      2809091.70     10268003.01
      2807606.07     10268328.33
#Sta/Elev= 30
  4254.6 1159.50  4443.9 1161.69  4524.0 1165.28  4564.1 1164.66  4804.4 1157.81
  4834.5 1152.88  4884.5 1155.14  4934.6 1154.46  4992.7 1147.95  4992.9 1147.45
  4996.7 1147.95  5034.7 1151.58  5152.5 1154.21  5257.6 1157.90  5356.7 1161.46
  5533.0 1168.41  5668.9 1178.22  5752.7 1181.20  5829.1 1184.94  5986.3 1183.15
  6163.3 1187.08  6390.0 1200.02  6416.2 1199.38  6483.9 1204.64  6489.0 1203.56
  6508.3 1207.44  6527.8 1208.60  6569.8 1207.05  6576.7 1206.23  6579.6 1203.98
#Mann=10,-1,0
  4254.6    0.05       0  4992.7    0.03       0  4996.7    0.05       0
  5152.5    0.12       0  5257.6    0.05       0  5356.7    0.12       0
  5533.0    0.05       0  5752.7    0.12       0  6163.3    0.05       0
  6390.0    0.12       0
Bank Sta=4992.7,4996.7
Exp/Cntr=0.3,0.1

Type RM Length L Ch R = 1,10186,844,844,844
BEGIN DESCRIPTION:
Mapping XS 352df779
END DESCRIPTION:
XS GIS Cut Line= 3
      2809753.58     10267851.10      2809189.36     10267764.30
      2808440.66     10267861.95
#Sta/Elev= 30
  4405.7 1158.07  4585.7 1159.61  4605.9 1158.49  4737.5 1156.61  4821.7 1154.38
  4828.5 1154.83  4858.9 1152.57  4957.0 1148.72  4980.9 1148.79  4990.3 1147.24
  4998.4 1146.99  4998.7 1146.49  5002.4 1146.99  5020.6 1149.23  5091.2 1152.78
  5141.6 1157.15  5181.8 1159.40  5236.4 1161.87  5303.0 1163.54  5323.1 1165.21
  5345.3 1164.51  5452.0 1165.95  5474.7 1167.10  5524.8 1167.97  5565.2 1169.85
  5575.3 1170.95  5589.3 1170.85  5666.0 1172.95  5701.6 1171.75  5731.6 1171.82
#Mann=9,-1,0
  4405.7    0.05       0  4957.0    0.12       0  4998.4    0.07       0
  5002.4    0.12       0  5181.8    0.05       0  5236.4    0.12       0
  5345.3    0.05       0  5452.0    0.12       0  5589.3    0.05       0
Bank Sta=4998.4,5002.4
Exp/Cntr=0.3,0.1

Type RM Length L Ch R = 1,9342,342,342,342
BEGIN DESCRIPTION:
Mapping XS 02957b7c
END DESCRIPTION:
XS GIS Cut Line= 4
      2809308.73     10266820.26      2809167.66     10267015.60
      2809145.96     10267341.12      2808962.15     10267578.98
#Sta/Elev= 30
  4602.0 1159.28  4684.9 1159.10  4714.3 1157.67  4728.9 1159.14  4735.2 1156.85
  4741.3 1158.24  4749.9 1156.04  4756.0 1157.02  4764.6 1155.68  4778.2 1155.87
  4785.5 1157.96  4827.6 1159.06  4850.5 1160.92  4870.5 1158.85  4900.6 1153.40
  4940.7 1142.57  4946.7 1139.90  4951.7 1142.54  4970.8 1139.25  4998.8 1137.54
  4999.1 1137.04  5002.8 1137.54  5010.8 1138.80  5020.9 1142.24  5040.9 1144.85
  5151.2 1147.20  5202.8 1149.95  5276.2 1152.09  5427.0 1154.94  5469.8 1157.02
#Mann=5,-1,0
  4602.0    0.05       0  4998.8    0.03       0  5002.8    0.05       0
  5202.8    0.12       0  5276.2    0.05       0
Bank Sta=4998.8,5002.8
Exp/Cntr=0.3,0.1

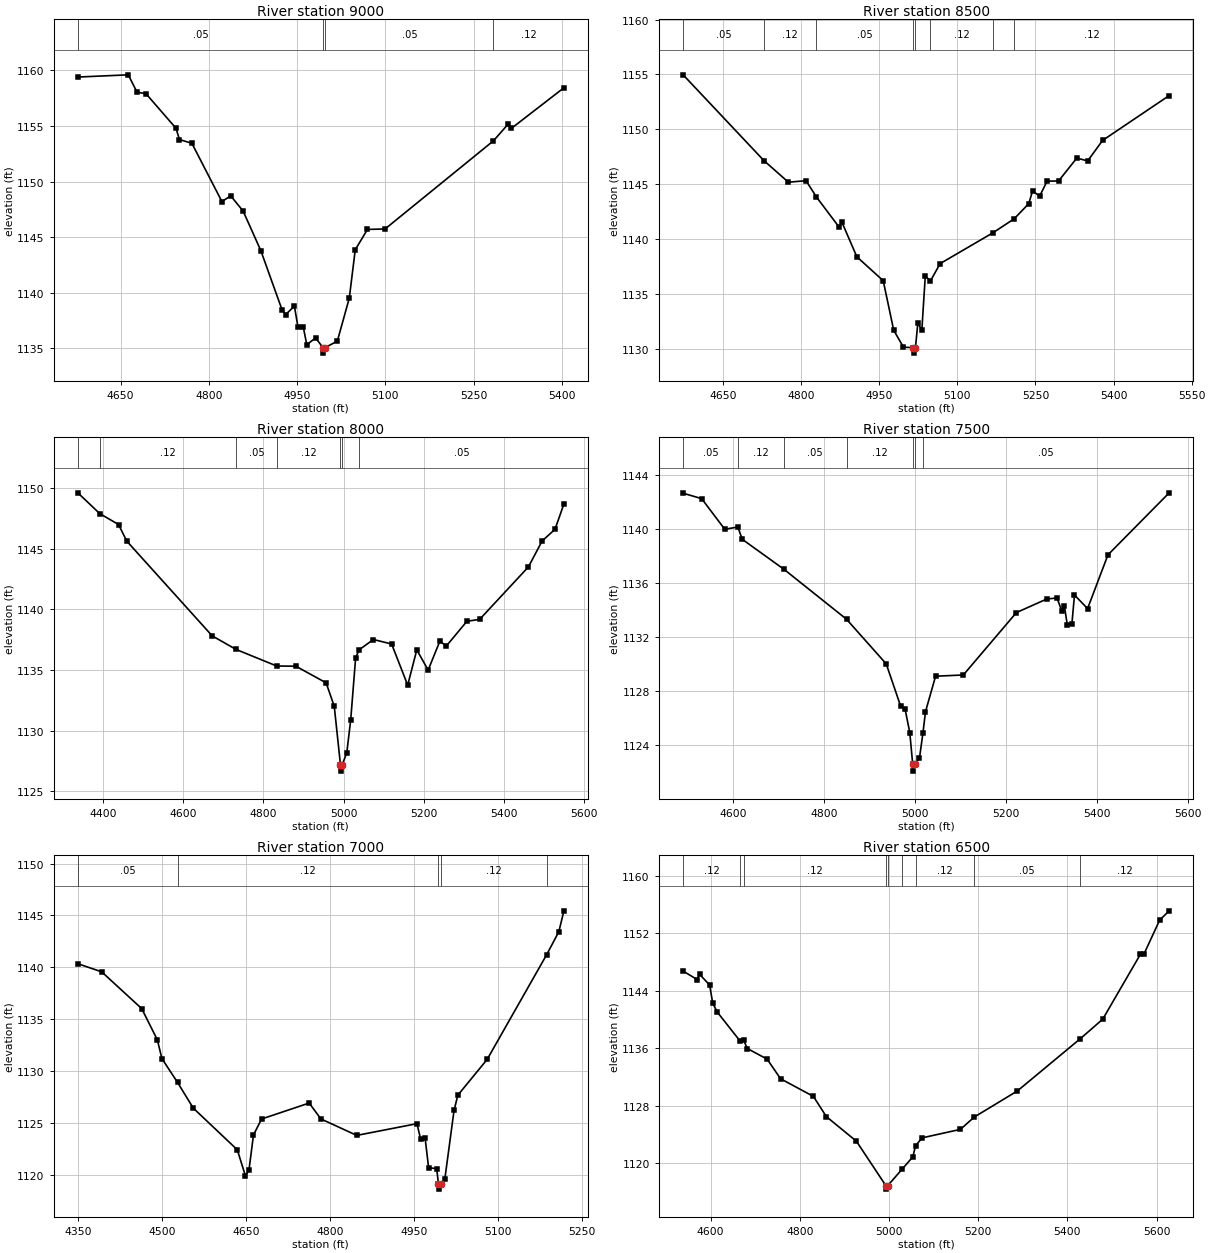
Type RM Length L Ch R = 1,9000,500,500,500
BEGIN DESCRIPTION:
SANFERNANDO042 18.0
END DESCRIPTION:
XS GIS Cut Line= 3
      2809105.70     10266903.09      2808871.25     10267254.93
      2808805.69     10267653.07
#Sta/Elev= 30
  4577.2 1159.41  4662.9 1159.61  4677.9 1158.04  4692.9 1157.92  4744.0 1154.80
  4750.0 1153.78  4771.0 1153.45  4822.1 1148.20  4837.1 1148.71  4858.2 1147.34
  4888.2 1143.79  4924.3 1138.46  4930.3 1138.01  4945.3 1138.79  4951.3 1136.94
  4960.4 1136.92  4966.4 1135.31  4981.4 1135.92  4993.9 1135.05  4994.2 1134.55
  4997.9 1135.05  5018.4 1135.64  5038.7 1139.51  5048.8 1143.86  5069.6 1145.69
  5099.5 1145.73  5283.8 1153.67  5309.2 1155.20  5314.3 1154.79  5403.5 1158.44
#Mann=4,-1,0
  4577.2    0.05       0  4993.9    0.05       0  4997.9    0.05       0
  5283.8    0.12       0
Bank Sta=4993.9,4997.9
Exp/Cntr=0.3,0.1

Type RM Length L Ch R = 1,8500,500,500,500
BEGIN DESCRIPTION:
SANFERNANDO042 17.0
END DESCRIPTION:
XS GIS Cut Line= 3
      2809005.65     10266853.12      2808583.72     10266916.75
      2808255.71     10267303.08
#Sta/Elev= 30
  4573.3 1154.97  4728.5 1147.15  4775.5 1145.18  4809.4 1145.32  4829.1 1143.85
  4873.3 1141.06  4878.4 1141.52  4907.0 1138.38  4957.6 1136.20  4977.8 1131.68
  4996.5 1130.14  5015.5 1130.10  5015.8 1129.60  5019.5 1130.10  5024.1 1132.34
  5031.8 1131.71  5038.4 1136.64  5048.2 1136.17  5066.9 1137.76  5168.3 1140.57
  5209.0 1141.84  5237.2 1143.23  5244.5 1144.40  5258.0 1143.90  5272.3 1145.28
  5294.3 1145.29  5329.4 1147.38  5350.3 1147.12  5378.9 1148.99  5506.8 1153.08
#Mann=8,-1,0
  4573.3    0.05       0  4728.5    0.12       0  4829.1    0.05       0
  5015.5    0.05       0  5019.5    0.05       0  5048.2    0.12       0
  5168.3    0.05       0  5209.0    0.12       0
Bank Sta=5015.5,5019.5
Exp/Cntr=0.3,0.1

Type RM Length L Ch R = 1,8000,500,500,500
BEGIN DESCRIPTION:
SANFERNANDO042 16.0
END DESCRIPTION:
XS GIS Cut Line= 3
      2808955.72     10266553.10      2808302.98     10266668.70
      2807805.66     10266903.12
#Sta/Elev= 30
  4337.1 1149.59  4391.7 1147.88  4438.7 1146.98  4459.0 1145.62  4672.3 1137.81
  4732.0 1136.69  4833.1 1135.33  4881.2 1135.31  4956.6 1133.94  4976.9 1132.00
  4992.4 1127.17  4992.7 1126.67  4996.4 1127.17  5008.1 1128.18  5017.8 1130.85
  5030.2 1136.00  5038.9 1136.66  5074.5 1137.51  5120.0 1137.14  5160.1 1133.75
  5182.8 1136.66  5211.1 1134.99  5240.2 1137.36  5256.7 1136.98  5307.8 1139.01
  5339.7 1139.17  5461.3 1143.49  5495.6 1145.63  5527.7 1146.59  5549.8 1148.67
#Mann=7,-1,0
  4337.1    0.05       0  4391.7    0.12       0  4732.0    0.05       0
  4833.1    0.12       0  4992.4    0.07       0  4996.4    0.12       0
  5038.9    0.05       0
Bank Sta=4992.4,4996.4
Exp/Cntr=0.3,0.1

Type RM Length L Ch R = 1,7500,500,500,500
BEGIN DESCRIPTION:
SANFERNANDO042 15.0
END DESCRIPTION:
XS GIS Cut Line= 3
      2808605.73     10266153.10      2808104.36     10266249.25
      2807605.66     10266503.12
#Sta/Elev= 30
  4489.5 1142.68  4530.3 1142.28  4581.2 1140.01  4610.0 1140.18  4619.6 1139.27
  4711.4 1137.05  4849.2 1133.35  4936.7 1130.04  4968.1 1126.94  4978.3 1126.67
  4988.5 1124.96  4995.0 1122.60  4995.2 1122.10  4999.0 1122.60  5009.7 1123.04
  5017.5 1124.92  5023.1 1126.50  5045.3 1129.13  5106.4 1129.22  5223.2 1133.84
  5290.3 1134.85  5312.7 1134.92  5323.2 1133.96  5328.8 1134.35  5335.2 1132.95
  5345.5 1133.02  5351.1 1135.14  5380.0 1134.14  5424.9 1138.12  5559.6 1142.71
#Mann=7,-1,0
  4489.5    0.05       0  4610.0    0.12       0  4711.4    0.05       0
  4849.2    0.12       0  4995.0    0.07       0  4999.0    0.12       0
  5017.5    0.05       0
Bank Sta=4995,4999
Exp/Cntr=0.3,0.1

Type RM Length L Ch R = 1,7000,500,500,500
BEGIN DESCRIPTION:
SANFERNANDO042 14.0
END DESCRIPTION:
XS GIS Cut Line= 3
      2808205.71     10265353.08      2807805.64     10265866.13
      2807605.64     10265953.13
#Sta/Elev= 30
  4349.4 1140.34  4392.0 1139.56  4463.6 1136.01  4491.5 1133.00  4499.6 1131.20
  4527.7 1128.89  4555.7 1126.42  4634.4 1122.40  4648.9 1119.89  4655.2 1120.43
  4663.3 1123.83  4677.8 1125.37  4762.9 1126.91  4783.7 1125.38  4847.9 1123.79
  4955.5 1124.92  4961.9 1123.46  4970.0 1123.56  4976.3 1120.69  4990.8 1120.57
  4993.9 1119.11  4994.1 1118.61  4997.9 1119.11  5005.2 1119.54  5021.8 1126.21
  5028.6 1127.67  5081.0 1131.12  5187.4 1141.22  5209.1 1143.43  5218.1 1145.44
#Mann=5,-1,0
  4349.4    0.05       0  4527.7    0.12       0  4993.9    0.07       0
  4997.9    0.12       0  5187.4    0.05       0
Bank Sta=4993.9,4997.9
Exp/Cntr=0.3,0.1

Type RM Length L Ch R = 1,6500,500,500,500
BEGIN DESCRIPTION:
SANFERNANDO042 13.0
END DESCRIPTION:
XS GIS Cut Line= 3
      2808155.68     10265203.11      2807738.93     10265401.36
      2807255.71     10265803.09
#Sta/Elev= 30
  4538.5 1146.75  4569.8 1145.58  4575.3 1146.31  4598.0 1144.81  4604.9 1142.27
  4615.2 1141.04  4666.4 1137.01  4674.2 1137.13  4682.5 1135.98  4726.8 1134.51
  4757.0 1131.78  4830.7 1129.32  4859.6 1126.52  4927.1 1123.09  4992.9 1116.93
  4993.2 1116.43  4997.6 1116.93  5030.3 1119.26  5053.6 1120.92  5059.8 1122.48
  5074.4 1123.56  5160.3 1124.74  5191.5 1126.46  5288.0 1130.08  5428.8 1137.33
  5479.4 1140.06  5564.0 1149.10  5571.8 1149.11  5607.0 1153.83  5628.4 1155.13
#Mann=9,-1,0
  4538.5    0.12       0  4666.4    0.05       0  4674.2    0.12       0
  4992.9    0.07       0  4997.6    0.12       0  5030.3    0.05       0
  5059.8    0.12       0  5191.5    0.05       0  5428.8    0.12       0
Bank Sta=4992.9,4997.6
Exp/Cntr=0.3,0.1