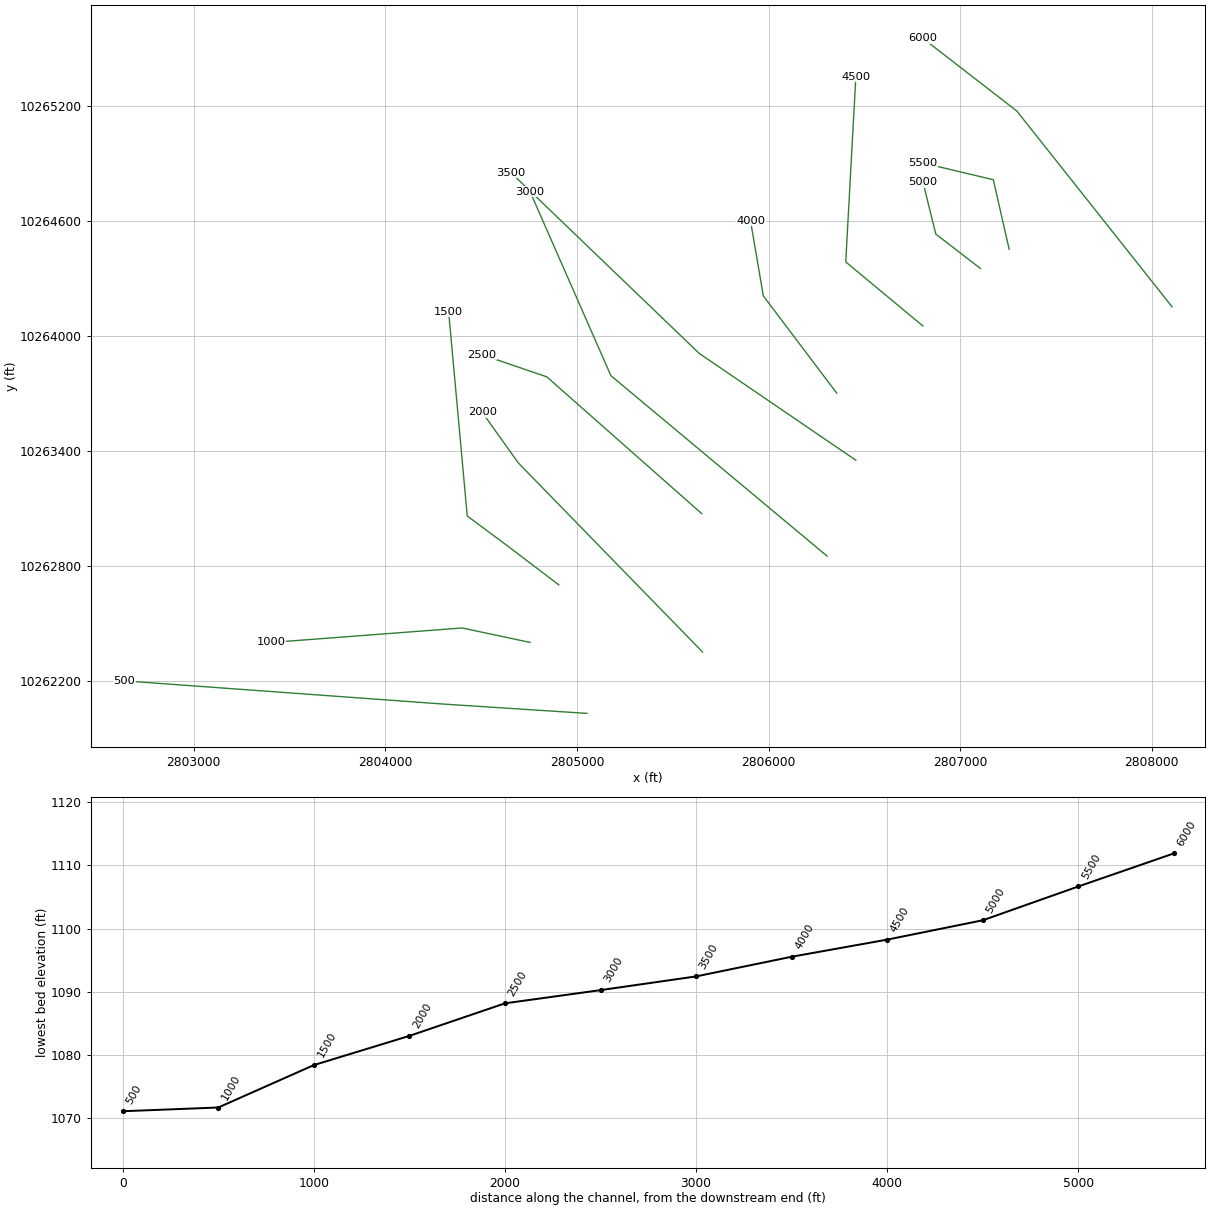
HEC-RAS study SANFERNANDO042.prj: SANFERNANDO042 Base Level Engineering

--- SANFERNANDO042.g01 (geometry) --- (continued)

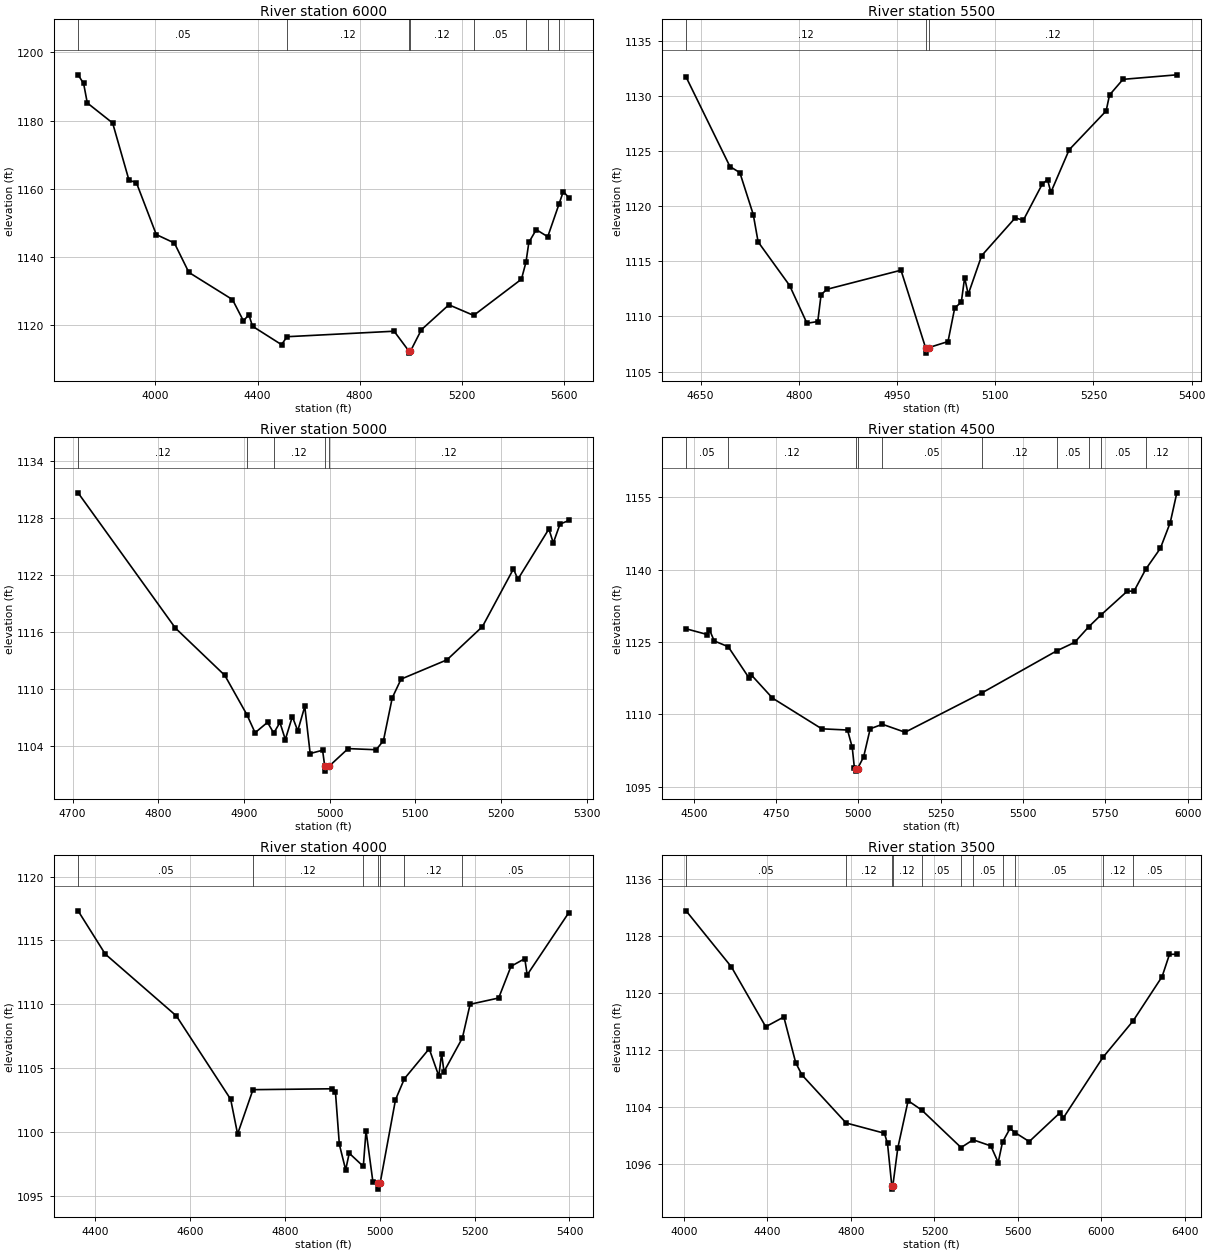
Type RM Length L Ch R = 1,6000,500,500,500
BEGIN DESCRIPTION:
SANFERNANDO042 12.0
END DESCRIPTION:
XS GIS Cut Line= 3
      2808105.69     10264153.10      2807295.64     10265174.09
      2806805.72     10265553.08
#Sta/Elev= 30
  3696.7 1193.44  3718.4 1190.90  3732.8 1185.20  3832.1 1179.32  3896.2 1162.55
  3925.1 1161.86  4003.1 1146.64  4074.0 1144.16  4130.7 1135.56  4301.6 1127.59
  4344.8 1121.31  4365.6 1123.21  4380.1 1119.78  4493.8 1114.38  4515.4 1116.71
  4934.9 1118.32  4993.8 1112.40  4994.2 1111.90  4998.5 1112.40  5041.7 1118.75
  5149.5 1126.06  5246.6 1122.95  5433.8 1133.56  5451.6 1138.58  5462.8 1144.35
  5491.8 1148.08  5536.8 1146.01  5580.8 1155.53  5597.7 1159.25  5619.4 1157.45
#Mann=8,-1,0
  3696.7    0.05       0  4515.4    0.12       0  4993.8    0.07       0
  4998.5    0.12       0  5246.6    0.05       0  5451.6    0.12       0
  5536.8    0.05       0  5580.8    0.12       0
Bank Sta=4993.8,4998.5
Exp/Cntr=0.3,0.1

Type RM Length L Ch R = 1,5500,500,500,500
BEGIN DESCRIPTION:
SANFERNANDO042 11.0
END DESCRIPTION:
XS GIS Cut Line= 3
      2807255.69     10264453.10      2807172.87     10264815.87
      2806805.69     10264903.11
#Sta/Elev= 30
  4627.9 1131.74  4694.9 1123.61  4710.0 1123.06  4730.5 1119.25  4737.9 1116.77
  4786.0 1112.81  4812.5 1109.38  4829.0 1109.54  4834.1 1111.99  4843.3 1112.47
  4956.1 1114.20  4993.6 1107.17  4994.0 1106.67  4998.5 1107.17  5027.9 1107.72
  5038.2 1110.78  5048.2 1111.29  5053.3 1113.52  5058.8 1112.01  5079.3 1115.52
  5130.7 1118.96  5142.8 1118.72  5171.8 1122.01  5179.9 1122.43  5185.0 1121.27
  5213.0 1125.14  5269.4 1128.66  5274.6 1130.11  5295.2 1131.53  5377.4 1131.94
#Mann=3,-1,0
  4627.9    0.12       0  4993.6    0.07       0  4998.5    0.12       0
Bank Sta=4993.6,4998.5
Exp/Cntr=0.3,0.1

Type RM Length L Ch R = 1,5000,500,500,500
BEGIN DESCRIPTION:
SANFERNANDO042 10.0
END DESCRIPTION:
XS GIS Cut Line= 3
      2807105.70     10264353.10      2806872.96     10264532.25
      2806805.68     10264803.12
#Sta/Elev= 30
  4706.3 1130.60  4819.9 1116.37  4877.6 1111.39  4903.4 1107.25  4912.9 1105.36
  4927.4 1106.45  4934.7 1105.32  4941.9 1106.44  4948.2 1104.64  4956.4 1107.06
  4962.7 1105.56  4970.9 1108.12  4977.2 1103.17  4991.7 1103.52  4994.2 1101.82
  4994.5 1101.32  4999.1 1101.82  5021.5 1103.69  5054.2 1103.57  5062.7 1104.52
  5073.0 1109.03  5083.3 1111.00  5136.9 1113.03  5178.3 1116.53  5214.5 1122.60
  5219.6 1121.50  5255.8 1126.79  5261.0 1125.33  5268.8 1127.31  5279.1 1127.69
#Mann=5,-1,0
  4706.3    0.12       0  4903.4    0.05       0  4934.7    0.12       0
  4994.2    0.07       0  4999.1    0.12       0
Bank Sta=4994.2,4999.1
Exp/Cntr=0.3,0.1

Type RM Length L Ch R = 1,4500,500,500,500
BEGIN DESCRIPTION:
SANFERNANDO042 9.0
END DESCRIPTION:
XS GIS Cut Line= 3
      2806805.66     10264053.13      2806402.90     10264387.24
      2806455.68     10265353.09
#Sta/Elev= 30
  4476.7 1127.73  4541.1 1126.54  4547.6 1127.56  4562.0 1125.22  4604.6 1124.02
  4668.8 1117.46  4675.3 1118.14  4739.1 1113.38  4888.8 1107.02  4967.0 1106.77
  4981.3 1103.21  4987.8 1098.99  4992.5 1098.76  4992.8 1098.26  4997.4 1098.76
  5015.9 1101.20  5035.9 1107.03  5073.0 1107.96  5141.9 1106.31  5376.1 1114.49
  5602.6 1123.17  5656.9 1124.92  5699.5 1128.13  5736.2 1130.55  5817.1 1135.54
  5837.1 1135.50  5873.1 1140.09  5917.2 1144.38  5947.3 1149.73  5967.3 1155.88
#Mann=10,-1,0
  4476.7    0.05       0  4604.6    0.12       0  4992.5    0.07       0
  4997.4    0.12       0  5073.0    0.05       0  5376.1    0.12       0
  5602.6    0.05       0  5699.5    0.12       0  5736.2    0.05       0
  5873.1    0.12       0
Bank Sta=4992.5,4997.4
Exp/Cntr=0.3,0.1

Type RM Length L Ch R = 1,4000,500,500,500
BEGIN DESCRIPTION:
SANFERNANDO042 8.0
END DESCRIPTION:
XS GIS Cut Line= 3
      2806355.67     10263703.14      2805972.78     10264210.22
      2805905.68     10264603.13
#Sta/Elev= 30
  4364.6 1117.32  4421.8 1113.94  4571.7 1109.10  4686.1 1102.58  4700.7 1099.86
  4733.1 1103.33  4900.5 1103.40  4906.8 1103.18  4915.1 1099.05  4928.4 1097.06
  4935.9 1098.36  4965.6 1097.33  4971.3 1100.13  4985.9 1096.09  4996.2 1096.05
  4996.6 1095.55  5001.2 1096.05  5033.4 1102.54  5052.2 1104.19  5104.4 1106.53
  5124.7 1104.39  5130.5 1106.15  5135.6 1104.74  5174.3 1107.37  5190.6 1110.01
  5250.8 1110.50  5276.8 1112.98  5305.8 1113.58  5310.9 1112.31  5398.6 1117.18
#Mann=7,-1,0
  4364.6    0.05       0  4733.1    0.12       0  4965.6    0.05       0
  4996.2    0.05       0  5001.2    0.05       0  5052.2    0.12       0
  5174.3    0.05       0
Bank Sta=4996.2,5001.2
Exp/Cntr=0.3,0.1

Type RM Length L Ch R = 1,3500,500,500,500
BEGIN DESCRIPTION:
SANFERNANDO042 7.0
END DESCRIPTION:
XS GIS Cut Line= 3
      2806455.68     10263353.11      2805637.86     10263910.50
      2804655.70     10264853.10
#Sta/Elev= 30
  4010.3 1131.53  4227.2 1123.66  4391.8 1115.25  4478.5 1116.62  4535.4 1110.20
  4565.3 1108.48  4777.0 1101.73  4960.3 1100.29  4975.2 1098.85  4995.7 1092.94
  4996.1 1092.44  5000.8 1092.94  5024.6 1098.23  5074.0 1104.86  5139.3 1103.54
  5327.6 1098.28  5385.2 1099.37  5470.2 1098.51  5505.5 1096.18  5526.1 1099.04
  5562.1 1100.96  5586.9 1100.37  5654.2 1099.12  5802.6 1103.20  5816.8 1102.41
  6007.0 1110.94  6151.8 1116.07  6290.7 1122.29  6325.9 1125.41  6361.3 1125.44
#Mann=11,-1,0
  4010.3    0.05       0  4777.0    0.12       0  4995.7    0.07       0
  5000.8    0.12       0  5139.3    0.05       0  5327.6    0.12       0
  5385.2    0.05       0  5526.1    0.12       0  5586.9    0.05       0
  6007.0    0.12       0  6151.8    0.05       0
Bank Sta=4995.7,5000.8
Exp/Cntr=0.3,0.1

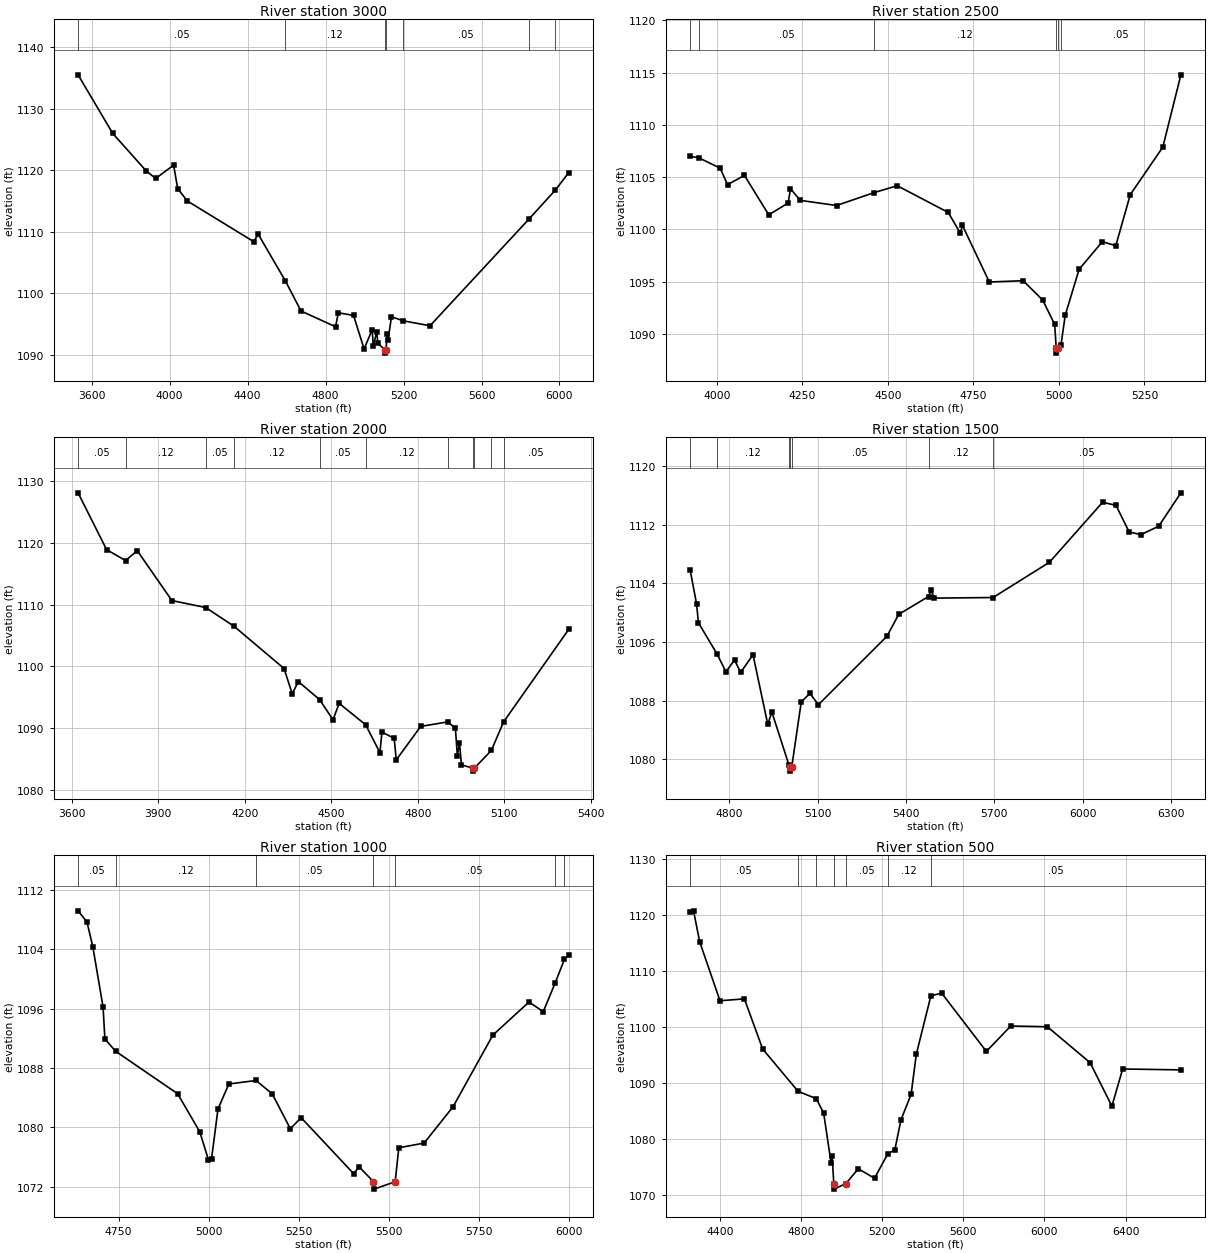
Type RM Length L Ch R = 1,3000,500,500,500
BEGIN DESCRIPTION:
SANFERNANDO042 6.0
END DESCRIPTION:
XS GIS Cut Line= 3
      2806305.68     10262853.12      2805177.47     10263794.07
      2804755.68     10264753.12
#Sta/Elev= 30
  3530.9 1135.53  3708.6 1126.00  3879.1 1119.95  3928.5 1118.67  4020.9 1120.84
  4041.8 1117.03  4091.2 1115.01  4432.3 1108.39  4454.4 1109.63  4593.5 1102.05
  4674.4 1097.12  4851.4 1094.56  4865.7 1096.83  4943.8 1096.40  4997.9 1090.95
  5039.4 1094.08  5044.9 1091.41  5062.8 1093.78  5068.2 1091.88  5105.6 1090.77
  5106.0 1090.27  5110.8 1090.77  5114.9 1093.40  5120.4 1092.37  5138.3 1096.18
  5199.9 1095.52  5336.0 1094.72  5842.2 1112.03  5978.0 1116.76  6047.7 1119.63
#Mann=7,-1,0
  3530.9    0.05       0  4593.5    0.12       0  5105.6    0.07       0
  5110.8    0.12       0  5199.9    0.05       0  5842.2    0.12       0
  5978.0    0.05       0
Bank Sta=5105.6,5110.8
Exp/Cntr=0.3,0.1

Type RM Length L Ch R = 1,2500,500,500,500
BEGIN DESCRIPTION:
SANFERNANDO042 5.0
END DESCRIPTION:
XS GIS Cut Line= 3
      2805651.36     10263074.79      2804843.16     10263787.85
      2804505.70     10263903.11
#Sta/Elev= 30
  3922.2 1106.99  3947.5 1106.85  4009.8 1105.86  4031.4 1104.28  4080.8 1105.17
  4151.9 1101.40  4208.8 1102.53  4215.4 1103.90  4243.9 1102.78  4350.1 1102.29
  4459.6 1103.52  4527.5 1104.18  4676.4 1101.63  4711.6 1099.67  4718.2 1100.38
  4796.6 1094.98  4895.6 1095.10  4952.5 1093.26  4987.6 1090.94  4992.2 1088.68
  4992.7 1088.18  4997.7 1088.68  5006.1 1088.94  5018.5 1091.80  5059.1 1096.19
  5127.0 1098.83  5166.4 1098.45  5208.7 1103.33  5303.8 1107.87  5356.6 1114.78
#Mann=6,-1,0
  3922.2    0.12       0  3947.5    0.05       0  4459.6    0.12       0
  4992.2    0.07       0  4997.7    0.12       0  5006.1    0.05       0
Bank Sta=4992.2,4997.7
Exp/Cntr=0.3,0.1

Type RM Length L Ch R = 1,2000,500,500,500
BEGIN DESCRIPTION:
SANFERNANDO042 4.0
END DESCRIPTION:
XS GIS Cut Line= 3
      2805655.72     10262353.08      2804693.76     10263339.76
      2804505.70     10263603.09
#Sta/Elev= 30
  3622.0 1128.16  3721.0 1118.94  3786.8 1117.18  3827.2 1118.78  3947.3 1110.69
  4064.5 1109.56  4163.3 1106.50  4336.2 1099.67  4364.5 1095.58  4385.8 1097.55
  4459.4 1094.63  4506.0 1091.36  4527.3 1094.02  4619.2 1090.54  4668.7 1086.02
  4675.7 1089.37  4718.1 1088.35  4725.3 1084.85  4810.0 1090.28  4903.6 1091.01
  4930.3 1090.01  4937.3 1085.45  4944.5 1087.67  4951.5 1084.03  4991.1 1083.53
  4991.6 1083.03  4996.6 1083.53  5055.2 1086.39  5097.3 1091.00  5323.6 1106.03
#Mann=11,-1,0
  3622.0    0.05       0  3786.8    0.12       0  4064.5    0.05       0
  4163.3    0.12       0  4459.4    0.05       0  4619.2    0.12       0
  4903.6    0.05       0  4991.1    0.05       0  4996.6    0.05       0
  5055.2    0.12       0  5097.3    0.05       0
Bank Sta=4991.1,4996.6
Exp/Cntr=0.3,0.1

Type RM Length L Ch R = 1,1500,500,500,500
BEGIN DESCRIPTION:
SANFERNANDO042 3.0
END DESCRIPTION:
XS GIS Cut Line= 4
      2804905.70     10262703.10      2804640.11     10262904.98
      2804427.86     10263062.46      2804330.68     10264128.14
#Sta/Elev= 30
  4666.4 1105.81  4688.2 1101.19  4694.5 1098.63  4757.5 1094.39  4788.0 1091.95
  4817.1 1093.56  4838.0 1091.86  4880.0 1094.27  4930.2 1084.78  4944.1 1086.47
  5001.6 1079.31  5005.7 1078.91  5006.1 1078.41  5011.4 1078.91  5044.0 1087.84
  5073.2 1089.01  5102.4 1087.47  5335.2 1096.79  5375.4 1099.78  5476.6 1102.21
  5485.9 1103.06  5495.9 1101.99  5695.8 1102.07  5887.5 1106.87  6068.3 1115.05
  6113.8 1114.64  6158.6 1111.00  6198.8 1110.65  6259.1 1111.79  6334.4 1116.34
#Mann=7,-1,0
  4666.4    0.05       0  4757.5    0.12       0  5001.6    0.05       0
  5005.7    0.07       0  5011.4    0.05       0  5476.6    0.12       0
  5695.8    0.05       0
Bank Sta=5005.7,5011.4
Exp/Cntr=0.3,0.1

Type RM Length L Ch R = 1,1000,500,500,500
BEGIN DESCRIPTION:
SANFERNANDO042 2.0
END DESCRIPTION:
XS GIS Cut Line= 3
      2804755.66     10262403.12      2804401.39     10262478.50
      2803405.64     10262403.11
#Sta/Elev= 30
  4637.8 1109.18  4662.6 1107.66  4678.7 1104.34  4707.0 1096.25  4712.2 1091.92
  4741.8 1090.27  4913.8 1084.55  4975.2 1079.43  4999.1 1075.68  5007.9 1075.78
  5025.8 1082.50  5055.9 1085.86  5131.3 1086.33  5176.2 1084.53  5226.4 1079.84
  5256.4 1081.32  5402.2 1073.77  5416.9 1074.72  5457.0 1072.70  5458.5 1071.70
  5517.2 1072.70  5527.2 1077.27  5597.4 1077.90  5677.6 1082.79  5788.0 1092.44
  5888.2 1096.90  5927.8 1095.60  5960.8 1099.46  5986.5 1102.65  5998.6 1103.21
#Mann=7,-1,0
  4637.8    0.05       0  4741.8    0.12       0  5131.3    0.05       0
  5457.0    0.07       0  5517.2    0.05       0  5960.8    0.12       0
  5986.5    0.05       0
Bank Sta=5457,5517.2
Exp/Cntr=0.3,0.1

Type RM Length L Ch R = 1,500,0,0,0
BEGIN DESCRIPTION:
SANFERNANDO042 1.0
END DESCRIPTION:
XS GIS Cut Line= 3
      2805052.37     10262033.16      2804307.53     10262081.38
      2802639.43     10262202.61
#Sta/Elev= 30
  4253.6 1120.39  4270.3 1120.68  4300.4 1115.18  4400.6 1104.66  4520.8 1105.00
  4611.0 1096.07  4785.3 1088.54  4875.4 1087.22  4911.7 1084.65  4948.0 1075.82
  4953.1 1077.08  4961.7 1072.11  4963.2 1071.11  5021.9 1072.11  5082.1 1074.74
  5162.3 1073.05  5227.4 1077.38  5262.5 1078.11  5292.6 1083.43  5342.7 1088.00
  5368.3 1095.13  5440.0 1105.52  5493.1 1106.03  5713.7 1095.64  5834.0 1100.17
  6014.5 1100.03  6225.1 1093.63  6332.4 1085.89  6385.5 1092.51  6672.5 1092.35
#Mann=7,-1,0
  4253.6    0.05       0  4785.3    0.12       0  4875.4    0.05       0
  4961.7    0.05       0  5021.9    0.05       0  5227.4    0.12       0
  5440.0    0.05       0
Bank Sta=4961.7,5021.9
Exp/Cntr=0.3,0.1

Chan Stop Cuts=-1