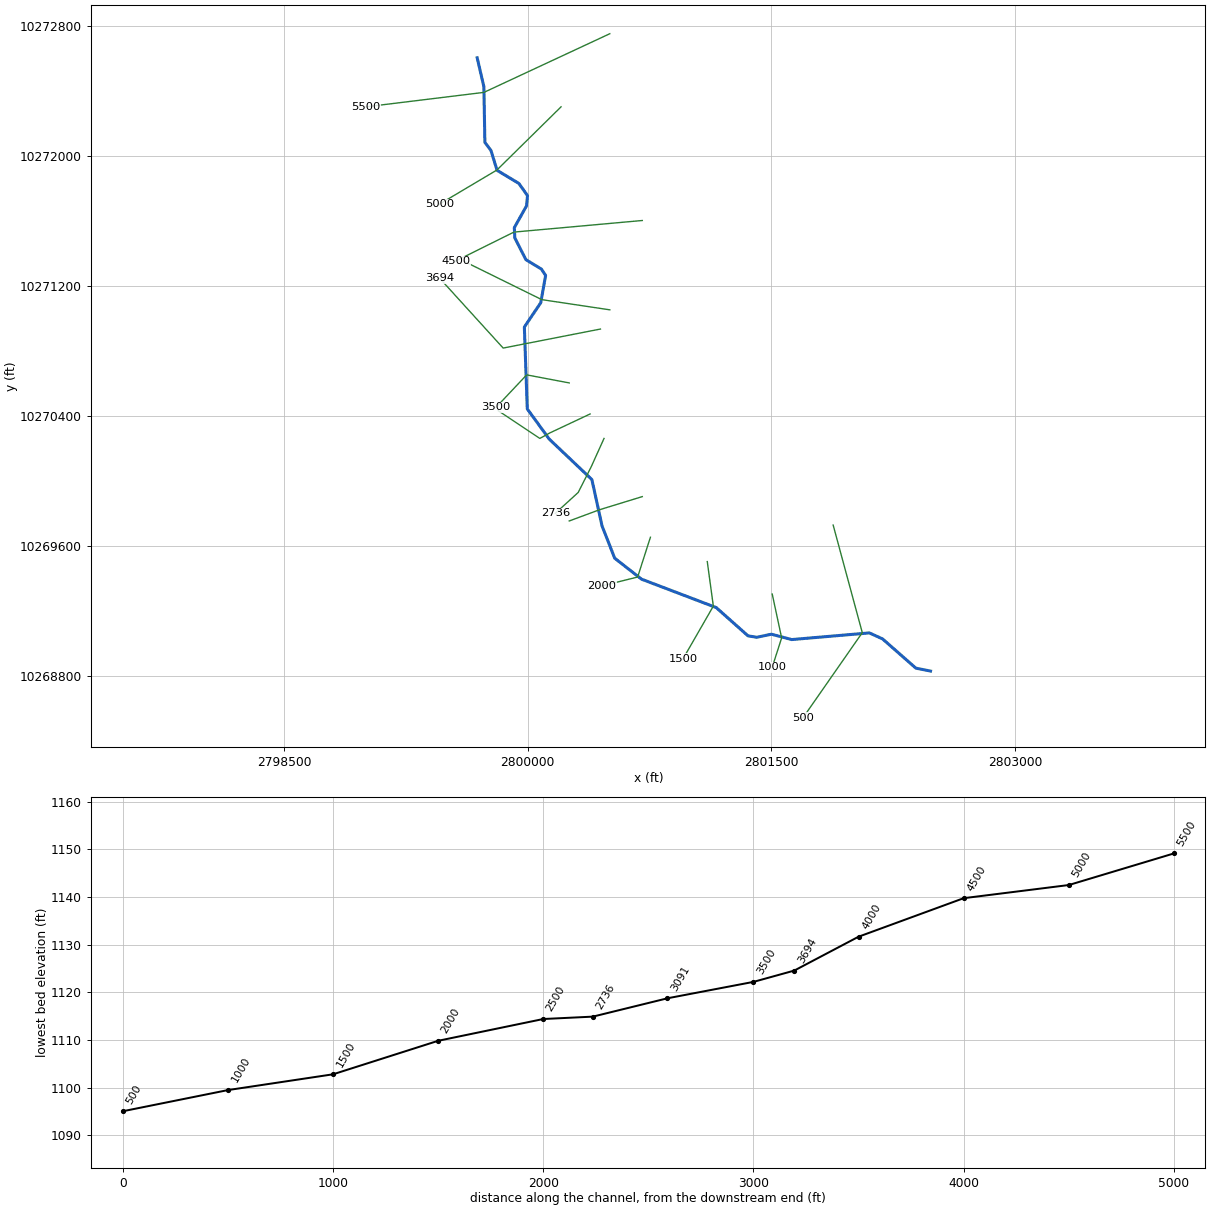
--- SANFERNANDO043.prj (project) ---

Proj Title=SANFERNANDO043 Base Level Engineering
Current Plan=p01
Default Exp/Contr=0.3,0.1
English Units
Geom File=g01
Flow File=f01
Plan File=p01
BEGIN DESCRIPTION:
SANFERNANDO043
END DESCRIPTION:

--- SANFERNANDO043.p01 (plan) ---

Plan Title=Multiple Run
Short Identifier=Multiple
Geom File=g01
Flow File=f01
Subcritical Flow
K Sum by GR= 0
Std Step Tol= 0.01
Critical Tol= 0.01
Num of Std Step Trials= 20
Max Error Tol= 0.3
Flow Tol Ratio= 0.001
Split Flow NTrial= 30
Split Flow Tol= 0.02
Split Flow Ratio= 0.02
Log Output Level= 0
Friction Slope Method= 1
Unsteady Friction Slope Method= 2
Unsteady Bridges Friction Slope Method= 1
Parabolic Critical Depth
Global Vel Dist=  1 , 1 , 1
Global Log Level= 0
CheckData=True
Encroach Param= -1, 0, 0, 0
BEGIN DESCRIPTION:
Multiple Run
END DESCRIPTION:

--- SANFERNANDO043.f01 (steady flow) ---

Flow Title=Multiple
Number of Profiles=7
Profile Names=10-year,25-year,50-year,1pct_min,100-year,1pct_plu,500-year
River Rch & RM= SANFERNANDO043,Reach-1,5500
     209     324     383     257     495     954     680
River Rch & RM= SANFERNANDO043,Reach-1,2736
     627    1022    1639     979    2227    5064    3041
Boundary for River Rch & Prof#=SANFERNANDO043,Reach-1,1
Up Type=0
Dn Type=3
Dn Slope=0.005
Boundary for River Rch & Prof#=SANFERNANDO043,Reach-1,2
Up Type=0
Dn Type=3
Dn Slope=0.005
Boundary for River Rch & Prof#=SANFERNANDO043,Reach-1,3
Up Type=0
Dn Type=3
Dn Slope=0.005
Boundary for River Rch & Prof#=SANFERNANDO043,Reach-1,4
Up Type=0
Dn Type=3
Dn Slope=0.005
Boundary for River Rch & Prof#=SANFERNANDO043,Reach-1,5
Up Type=0
Dn Type=3
Dn Slope=0.005
Boundary for River Rch & Prof#=SANFERNANDO043,Reach-1,6
Up Type=0
Dn Type=3
Dn Slope=0.005
Boundary for River Rch & Prof#=SANFERNANDO043,Reach-1,7
Up Type=0
Dn Type=3
Dn Slope=0.005

--- SANFERNANDO043.g01 (geometry) ---

Geom Title=Existing Conditions

River Reach=SANFERNANDO043,Reach-1
Reach XY= 30
      2799689.00     10272605.00      2799730.25     10272427.00
      2799736.50     10272084.00      2799774.00     10272034.00
      2799811.50     10271912.00      2799946.00     10271831.00
      2799999.00     10271756.00      2799992.75     10271693.00
      2799917.75     10271559.00      2799920.75     10271496.00
      2799989.00     10271362.00      2800084.50     10271304.00
      2800110.50     10271265.00      2800080.50     10271097.00
      2799979.50     10270947.00      2799997.50     10270443.00
      2800133.00     10270257.00      2800395.25     10270008.00
      2800457.75     10269723.00      2800535.75     10269524.00
      2800700.75     10269395.00      2801160.75     10269220.00
      2801356.50     10269046.00      2801410.25     10269037.00
      2801500.75     10269056.00      2801625.50     10269023.00
      2802103.50     10269064.00      2802185.00     10269027.00
      2802390.00     10268847.00      2802480.25     10268829.00

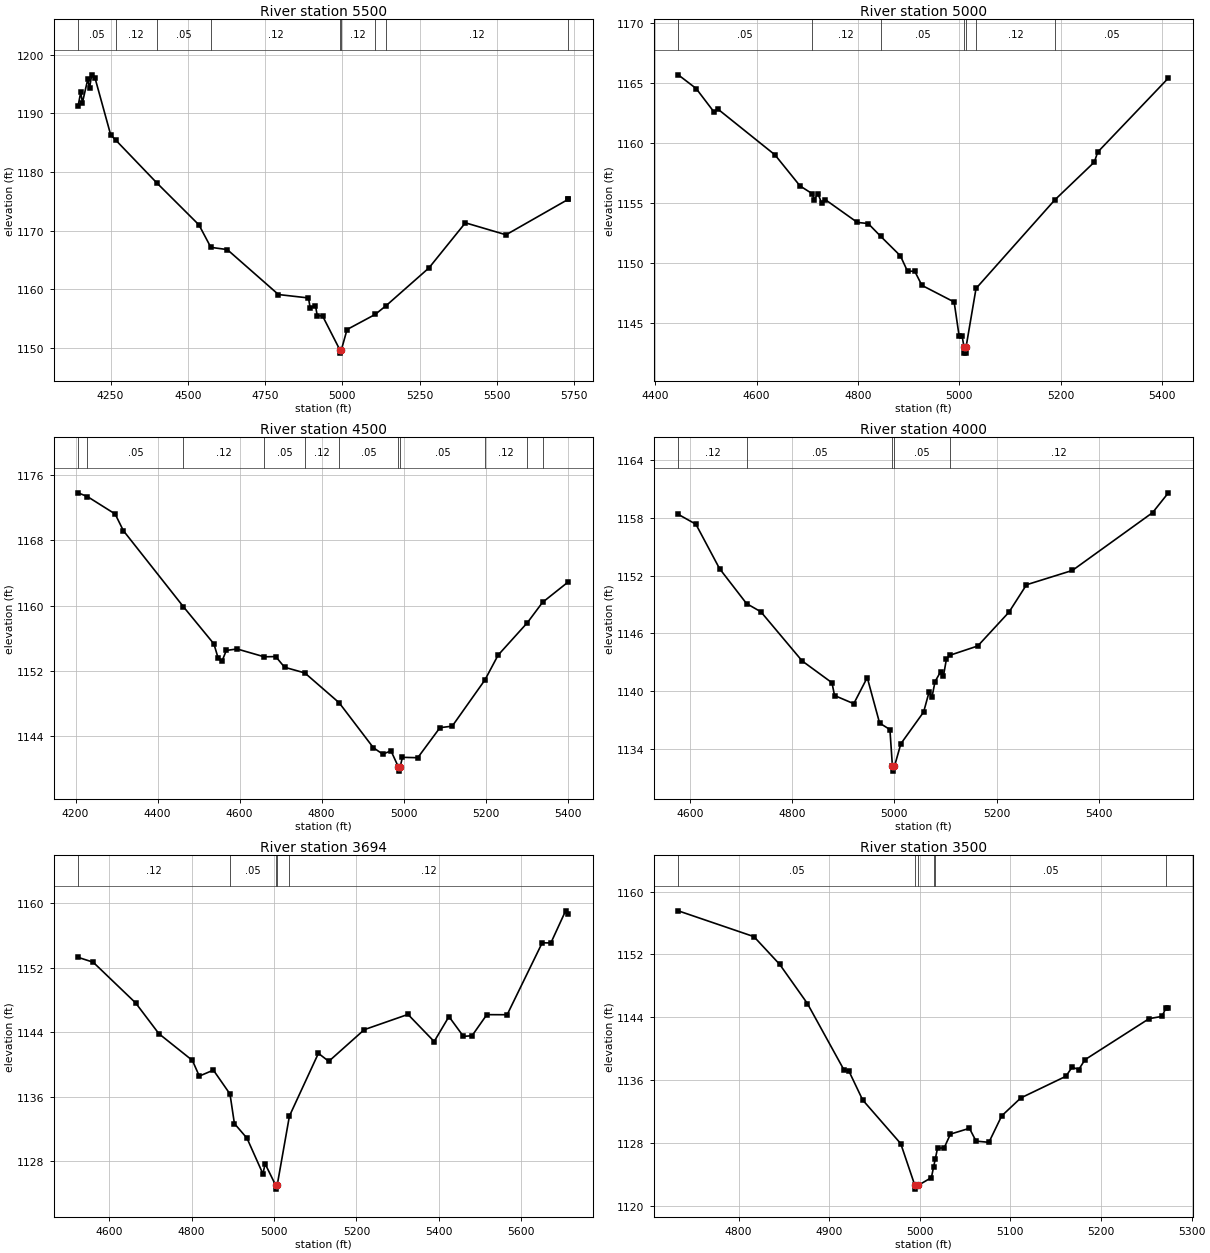
Type RM Length L Ch R = 1,5500,500,500,500
BEGIN DESCRIPTION:
SANFERNANDO043 11.0
END DESCRIPTION:
XS GIS Cut Line= 3
      2800505.72     10272753.13      2799730.64     10272391.94
      2799005.66     10272303.11
#Sta/Elev= 30
  4144.9 1191.19  4153.6 1193.57  4159.1 1191.80  4176.5 1195.82  4182.0 1194.24
  4189.1 1196.54  4199.4 1196.08  4250.6 1186.29  4266.8 1185.42  4399.3 1178.15
  4536.1 1170.97  4574.5 1167.15  4627.6 1166.77  4793.2 1159.11  4890.2 1158.53
  4895.7 1156.89  4913.0 1157.20  4918.6 1155.54  4935.9 1155.46  4992.4 1149.63
  4992.7 1149.13  4996.4 1149.63  5015.1 1153.15  5106.0 1155.72  5142.0 1157.24
  5280.1 1163.65  5397.9 1171.33  5529.4 1169.29  5730.1 1175.32  5730.4 1175.32
#Mann=9,-1,0
  4144.9    0.05       0  4266.8    0.12       0  4399.3    0.05       0
  4574.5    0.12       0  4992.4    0.07       0  4996.4    0.12       0
  5106.0    0.05       0  5142.0    0.12       0  5730.1    0.05       0
Bank Sta=4992.4,4996.4
Exp/Cntr=0.3,0.1

Type RM Length L Ch R = 1,5000,500,500,500
BEGIN DESCRIPTION:
SANFERNANDO043 10.0
END DESCRIPTION:
XS GIS Cut Line= 3
      2800205.67     10272303.09      2799810.61     10271913.99
      2799455.73     10271703.14
#Sta/Elev= 30
  4445.5 1165.69  4480.8 1164.55  4516.1 1162.59  4523.3 1162.85  4636.4 1159.02
  4685.9 1156.43  4709.4 1155.80  4714.1 1155.30  4721.3 1155.78  4728.3 1155.02
  4735.4 1155.30  4799.0 1153.39  4820.3 1153.30  4845.1 1152.23  4883.9 1150.61
  4898.0 1149.32  4912.2 1149.33  4926.3 1148.15  4990.0 1146.76  4999.9 1143.91
  5005.8 1143.91  5009.5 1143.00  5009.8 1142.50  5013.3 1142.50  5013.5 1143.00
  5033.2 1147.89  5188.5 1155.26  5266.7 1158.42  5273.3 1159.25  5412.8 1165.42
#Mann=7,-1,0
  4445.5    0.05       0  4709.4    0.12       0  4845.1    0.05       0
  5009.5    0.05       0  5013.5    0.05       0  5033.2    0.12       0
  5188.5    0.05       0
Bank Sta=5009.5,5013.5
Exp/Cntr=0.3,0.1

Type RM Length L Ch R = 1,4500,500,500,500
BEGIN DESCRIPTION:
SANFERNANDO043 9.0
END DESCRIPTION:
XS GIS Cut Line= 3
      2800705.69     10271603.11      2799915.11     10271531.69
      2799555.72     10271353.13
#Sta/Elev= 30
  4206.2 1173.80  4229.1 1173.34  4296.6 1171.21  4316.7 1169.17  4463.1 1159.86
  4537.5 1155.31  4547.6 1153.60  4557.6 1153.24  4567.7 1154.51  4594.0 1154.69
  4660.3 1153.73  4688.2 1153.76  4709.8 1152.45  4759.1 1151.76  4842.8 1148.11
  4926.4 1142.60  4949.2 1141.82  4969.3 1142.22  4987.4 1140.24  4987.6 1139.74
  4991.4 1140.24  4997.2 1141.43  5034.5 1141.38  5088.7 1145.06  5118.5 1145.24
  5198.2 1150.89  5230.5 1153.94  5301.7 1157.90  5338.9 1160.40  5401.3 1162.89
#Mann=11,-1,0
  4206.2    0.12       0  4229.1    0.05       0  4463.1    0.12       0
  4660.3    0.05       0  4759.1    0.12       0  4842.8    0.05       0
  4987.4    0.05       0  4991.4    0.05       0  5198.2    0.12       0
  5301.7    0.05       0  5338.9    0.12       0
Bank Sta=4987.4,4991.4
Exp/Cntr=0.3,0.1

Type RM Length L Ch R = 1,4000,306,306,306
BEGIN DESCRIPTION:
SANFERNANDO043 8.0
END DESCRIPTION:
XS GIS Cut Line= 3
      2800505.72     10271053.11      2800086.99     10271115.82
      2799605.70     10271353.10
#Sta/Elev= 30
  4576.6 1158.39  4611.2 1157.36  4657.5 1152.74  4710.4 1149.10  4738.4 1148.25
  4819.3 1143.13  4877.7 1140.86  4882.7 1139.53  4920.4 1138.68  4946.8 1141.40
  4971.0 1136.66  4991.2 1135.99  4996.1 1132.16  4996.4 1131.66  5000.1 1132.16
  5012.6 1134.51  5057.2 1137.81  5067.9 1139.90  5073.5 1139.33  5079.5 1140.97
  5090.4 1142.00  5095.9 1141.52  5101.8 1143.30  5108.0 1143.71  5163.3 1144.69
  5224.4 1148.21  5258.7 1151.06  5348.5 1152.55  5505.7 1158.57  5536.6 1160.63
#Mann=5,-1,0
  4576.6    0.12       0  4710.4    0.05       0  4996.1    0.05       0
  5000.1    0.05       0  5108.0    0.12       0
Bank Sta=4996.1,5000.1
Exp/Cntr=0.3,0.1

Type RM Length L Ch R = 1,3694,194,194,194
BEGIN DESCRIPTION:
Mapping XS 325cbc3a
END DESCRIPTION:
XS GIS Cut Line= 3
      2800447.99     10270934.87      2799849.00     10270817.68
      2799459.56     10271246.07
#Sta/Elev= 30
  4524.5 1153.26  4561.1 1152.66  4664.1 1147.62  4720.7 1143.80  4802.0 1140.49
  4818.7 1138.55  4852.9 1139.29  4893.2 1136.33  4903.9 1132.67  4934.4 1130.86
  4973.2 1126.43  4978.3 1127.70  5003.8 1125.05  5004.0 1124.55  5007.8 1125.05
  5037.4 1133.60  5107.7 1141.37  5132.9 1140.38  5219.0 1144.30  5325.1 1146.19
  5388.6 1142.83  5424.5 1145.92  5459.6 1143.47  5480.5 1143.55  5516.4 1146.16
  5565.7 1146.15  5650.8 1155.06  5671.8 1155.04  5707.6 1159.02  5713.8 1158.57
#Mann=5,-1,0
  4524.5    0.12       0  4893.2    0.05       0  5003.8    0.05       0
  5007.8    0.05       0  5037.4    0.12       0
Bank Sta=5003.8,5007.8
Exp/Cntr=0.3,0.1

Type RM Length L Ch R = 1,3500,409,409,409
BEGIN DESCRIPTION:
SANFERNANDO043 7.0
END DESCRIPTION:
XS GIS Cut Line= 3
      2800255.66     10270603.12      2799993.82     10270652.74
      2799805.69     10270453.12
#Sta/Elev= 30
  4733.5 1157.55  4817.0 1154.27  4845.4 1150.75  4876.0 1145.77  4916.5 1137.30
  4921.6 1137.23  4937.0 1133.51  4979.0 1127.96  4994.5 1122.68  4994.8 1122.18
  4998.5 1122.68  5012.8 1123.64  5015.3 1125.02  5017.0 1125.95  5019.6 1127.38
  5026.9 1127.42  5033.8 1129.17  5054.8 1129.91  5062.1 1128.28  5076.3 1128.13
  5090.4 1131.49  5111.5 1133.77  5161.2 1136.52  5168.1 1137.68  5175.4 1137.38
  5182.3 1138.63  5253.1 1143.85  5267.2 1144.13  5271.6 1145.19  5274.3 1145.19
#Mann=6,-1,0
  4733.5    0.05       0  4994.5    0.05       0  4998.5    0.05       0
  5015.3    0.12       0  5017.0    0.05       0  5271.6    0.12       0
Bank Sta=4994.5,4998.5
Exp/Cntr=0.3,0.1

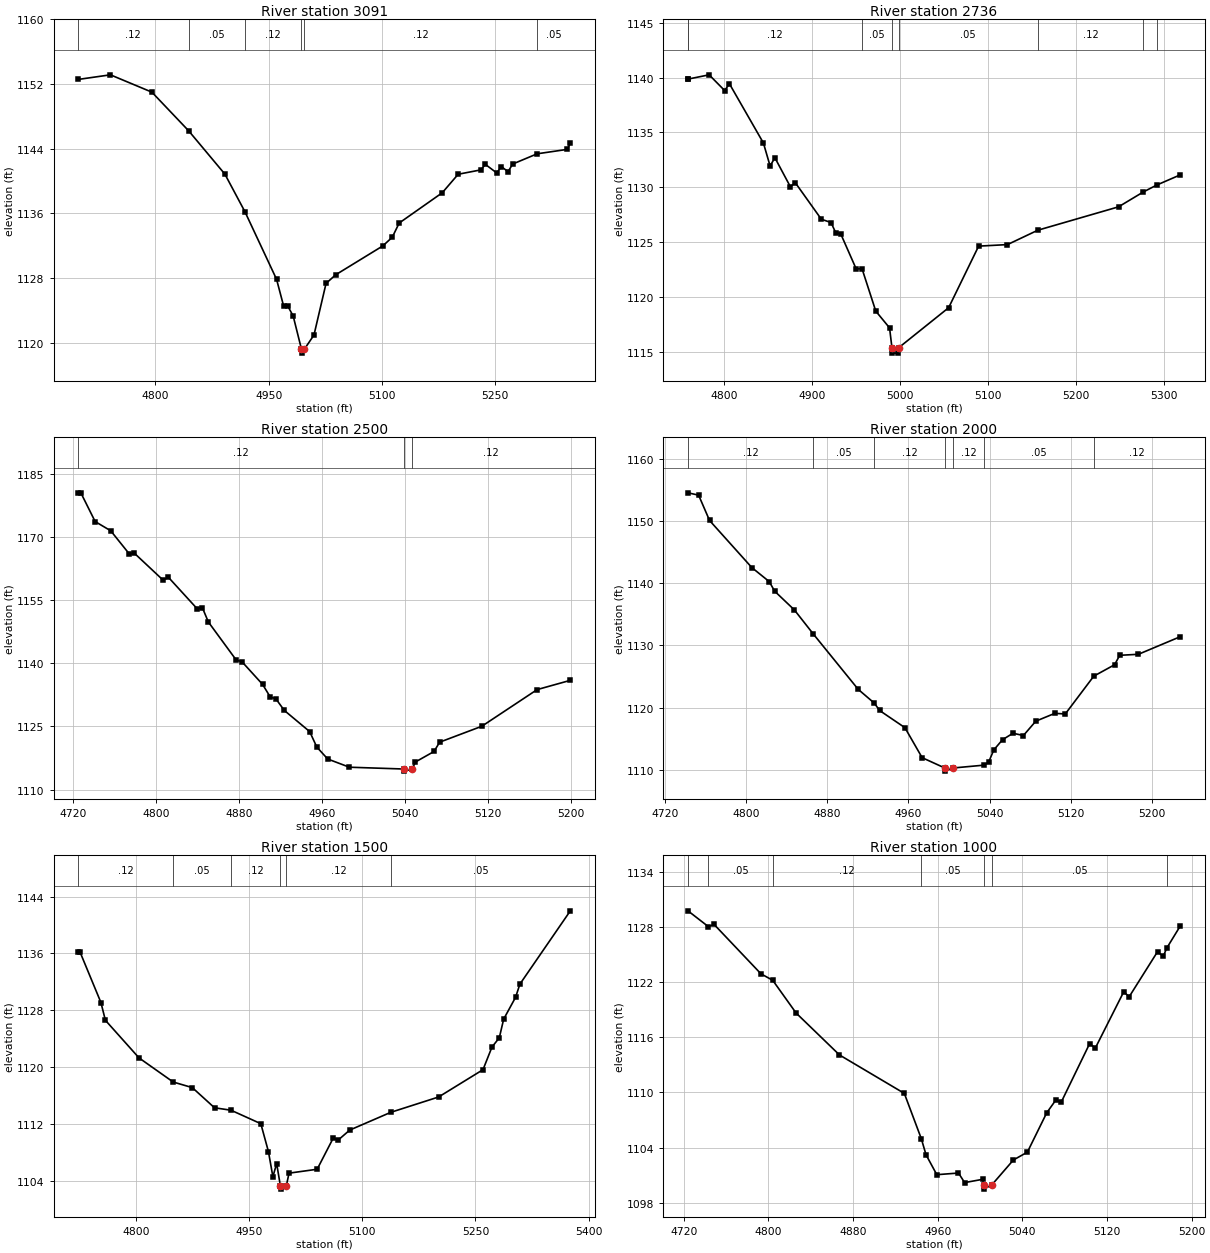
Type RM Length L Ch R = 1,3091,355,355,355
BEGIN DESCRIPTION:
Mapping XS 6bf0ccf7
END DESCRIPTION:
XS GIS Cut Line= 4
      2800384.30     10270411.91      2800135.47     10270294.82
      2800074.83     10270261.36      2799819.11     10270431.84
#Sta/Elev= 30
  4697.7 1152.57  4740.4 1153.14  4795.3 1151.00  4843.9 1146.23  4892.0 1140.86
  4918.5 1136.22  4960.4 1127.86  4969.8 1124.53  4975.4 1124.53  4982.4 1123.32
  4993.3 1119.24  4993.6 1118.74  4997.3 1119.24  5009.9 1120.98  5025.9 1127.36
  5038.6 1128.42  5101.0 1131.99  5113.6 1133.07  5122.7 1134.82  5179.7 1138.56
  5200.8 1140.85  5230.8 1141.39  5236.8 1142.07  5251.9 1141.01  5257.9 1141.80
  5266.9 1141.17  5272.9 1142.11  5305.4 1143.38  5345.0 1143.92  5349.3 1144.67
#Mann=6,-1,0
  4697.7    0.12       0  4843.9    0.05       0  4918.5    0.12       0
  4993.3    0.07       0  4997.3    0.12       0  5305.4    0.05       0
Bank Sta=4993.3,4997.3
Exp/Cntr=0.3,0.1

Type RM Length L Ch R = 1,2736,236,236,236
BEGIN DESCRIPTION:
Mapping XS c740ef95
END DESCRIPTION:
XS GIS Cut Line= 4
      2800470.05     10270261.32      2800390.60     10270085.69
      2800311.14     10269928.85      2800169.84     10269800.02
#Sta/Elev= 30
  4758.8 1139.84  4759.4 1139.87  4782.9 1140.25  4800.5 1138.82  4806.0 1139.43
  4844.6 1134.04  4852.2 1131.95  4857.7 1132.69  4875.3 1130.05  4880.8 1130.43
  4910.5 1127.09  4921.5 1126.79  4927.0 1125.84  4932.5 1125.77  4950.1 1122.57
  4956.8 1122.58  4972.4 1118.72  4988.1 1117.19  4990.8 1115.39  4991.3 1114.89
  4998.1 1114.89  4998.6 1115.39  5055.3 1119.03  5089.4 1124.64  5122.2 1124.78
  5156.7 1126.09  5248.5 1128.22  5276.8 1129.58  5292.1 1130.21  5318.6 1131.13
#Mann=8,-1,0
  4758.8    0.05       0  4759.4    0.12       0  4956.8    0.05       0
  4990.8    0.05       0  4998.6    0.05       0  5156.7    0.12       0
  5276.8    0.05       0  5292.1    0.12       0
Bank Sta=4990.8,4998.6
Exp/Cntr=0.3,0.1

Type RM Length L Ch R = 1,2500,500,500,500
BEGIN DESCRIPTION:
SANFERNANDO043 5.0
END DESCRIPTION:
XS GIS Cut Line= 3
      2800705.67     10269903.11      2800442.76     10269822.46
      2800255.70     10269753.12
#Sta/Elev= 30
  4725.0 1180.54  4727.6 1180.54  4741.4 1173.71  4756.4 1171.52  4774.1 1166.08
  4779.3 1166.16  4806.8 1159.81  4812.1 1160.44  4839.6 1153.02  4844.8 1153.22
  4850.5 1149.85  4877.5 1140.76  4882.8 1140.43  4902.8 1135.01  4910.3 1131.97
  4915.5 1131.62  4923.7 1128.83  4948.2 1123.79  4955.1 1120.10  4965.6 1117.27
  4986.5 1115.32  5039.1 1114.89  5039.6 1114.39  5047.0 1114.89  5050.2 1116.57
  5068.1 1119.06  5073.5 1121.27  5114.2 1125.06  5167.5 1133.77  5199.5 1135.97
#Mann=3,-1,0
  4725.0    0.12       0  5039.1    0.07       0  5047.0    0.12       0
Bank Sta=5039.1,5047
Exp/Cntr=0.3,0.1

Type RM Length L Ch R = 1,2000,500,500,500
BEGIN DESCRIPTION:
SANFERNANDO043 4.0
END DESCRIPTION:
XS GIS Cut Line= 3
      2800755.67     10269653.07      2800676.98     10269407.89
      2800455.66     10269353.11
#Sta/Elev= 30
  4742.5 1154.51  4753.0 1154.14  4763.8 1150.07  4805.5 1142.51  4822.7 1140.25
  4828.0 1138.72  4847.5 1135.70  4865.8 1131.91  4910.5 1122.94  4926.4 1120.73
  4931.5 1119.56  4956.5 1116.80  4973.5 1111.98  4995.9 1110.32  4996.4 1109.82
  5003.8 1110.32  5034.5 1110.78  5039.0 1111.23  5044.2 1113.23  5052.8 1114.87
  5063.1 1115.90  5073.4 1115.54  5085.6 1117.84  5104.4 1119.10  5114.7 1119.00
  5142.8 1125.07  5163.3 1126.90  5168.4 1128.42  5186.8 1128.58  5228.0 1131.40
#Mann=7,-1,0
  4742.5    0.12       0  4865.8    0.05       0  4926.4    0.12       0
  4995.9    0.07       0  5003.8    0.12       0  5034.5    0.05       0
  5142.8    0.12       0
Bank Sta=4995.9,5003.8
Exp/Cntr=0.3,0.1

Type RM Length L Ch R = 1,1500,500,500,500
BEGIN DESCRIPTION:
SANFERNANDO043 3.0
END DESCRIPTION:
XS GIS Cut Line= 3
      2801105.69     10269503.08      2801143.08     10269228.91
      2800955.66     10268903.07
#Sta/Elev= 30
  4723.3 1136.19  4725.8 1136.19  4753.5 1129.08  4759.4 1126.58  4804.0 1121.28
  4849.3 1117.88  4874.7 1117.09  4904.1 1114.25  4925.9 1113.91  4965.5 1112.01
  4975.6 1108.08  4981.5 1104.54  4986.5 1106.39  4991.4 1103.29  4991.9 1102.79
  4999.4 1103.29  5002.9 1105.04  5040.2 1105.59  5061.8 1110.04  5067.6 1109.66
  5083.4 1111.11  5137.8 1113.61  5201.2 1115.77  5260.1 1119.62  5272.0 1122.81
  5281.7 1124.11  5287.5 1126.74  5303.3 1129.82  5309.0 1131.67  5375.9 1142.00
#Mann=6,-1,0
  4723.3    0.12       0  4849.3    0.05       0  4925.9    0.12       0
  4991.4    0.07       0  4999.4    0.12       0  5137.8    0.05       0
Bank Sta=4991.4,4999.4
Exp/Cntr=0.3,0.1

Type RM Length L Ch R = 1,1000,500,500,500
BEGIN DESCRIPTION:
SANFERNANDO043 2.0
END DESCRIPTION:
XS GIS Cut Line= 3
      2801505.69     10269303.09      2801563.58     10269033.13
      2801505.68     10268853.11
#Sta/Elev= 30
  4723.9 1129.74  4743.2 1128.02  4748.6 1128.26  4792.9 1122.89  4804.0 1122.19
  4826.1 1118.63  4867.1 1114.07  4928.4 1109.89  4944.5 1104.95  4948.9 1103.22
  4959.1 1101.05  4979.6 1101.23  4985.4 1100.19  5002.6 1100.55  5003.3 1099.98
  5003.8 1099.48  5011.4 1099.98  5031.5 1102.65  5044.7 1103.50  5063.0 1107.78
  5071.5 1109.15  5076.8 1108.96  5103.6 1115.31  5108.9 1114.81  5135.7 1120.92
  5141.0 1120.41  5167.8 1125.31  5173.1 1124.78  5176.3 1125.66  5189.1 1128.07
#Mann=7,-1,0
  4723.9    0.12       0  4743.2    0.05       0  4804.0    0.12       0
  4944.5    0.05       0  5003.3    0.05       0  5011.4    0.05       0
  5176.3    0.12       0
Bank Sta=5003.3,5011.4
Exp/Cntr=0.3,0.1

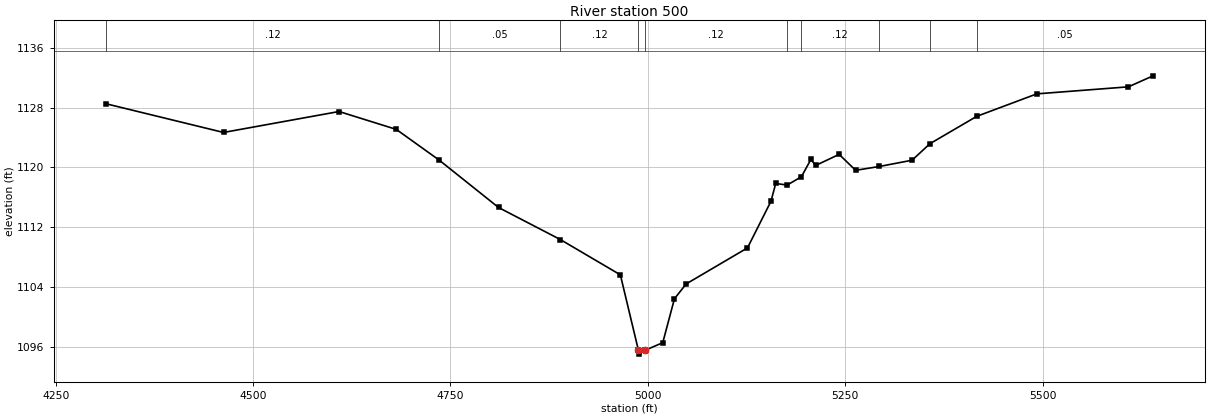
Type RM Length L Ch R = 1,500,0,0,0
BEGIN DESCRIPTION:
SANFERNANDO043 1.0
END DESCRIPTION:
XS GIS Cut Line= 3
      2801880.69     10269728.11      2802060.08     10269065.56
      2801694.29     10268540.52
#Sta/Elev= 30
  4313.6 1128.51  4462.6 1124.67  4608.9 1127.47  4681.4 1125.08  4735.9 1120.96
  4810.9 1114.64  4889.3 1110.35  4965.2 1105.64  4988.1 1095.54  4988.6 1095.04
  4996.2 1095.54  5018.9 1096.57  5033.7 1102.44  5048.5 1104.42  5126.2 1109.24
  5155.9 1115.46  5162.0 1117.85  5176.5 1117.64  5194.5 1118.75  5206.5 1121.06
  5212.6 1120.26  5242.3 1121.74  5263.2 1119.61  5293.1 1120.12  5334.7 1120.96
  5357.2 1123.16  5416.5 1126.82  5492.7 1129.83  5608.7 1130.77  5639.9 1132.24
#Mann=10,-1,0
  4313.6    0.12       0  4735.9    0.05       0  4889.3    0.12       0
  4988.1    0.07       0  4996.2    0.12       0  5176.5    0.05       0
  5194.5    0.12       0  5293.1    0.05       0  5357.2    0.12       0
  5416.5    0.05       0
Bank Sta=4988.1,4996.2
Exp/Cntr=0.3,0.1

Chan Stop Cuts=-1