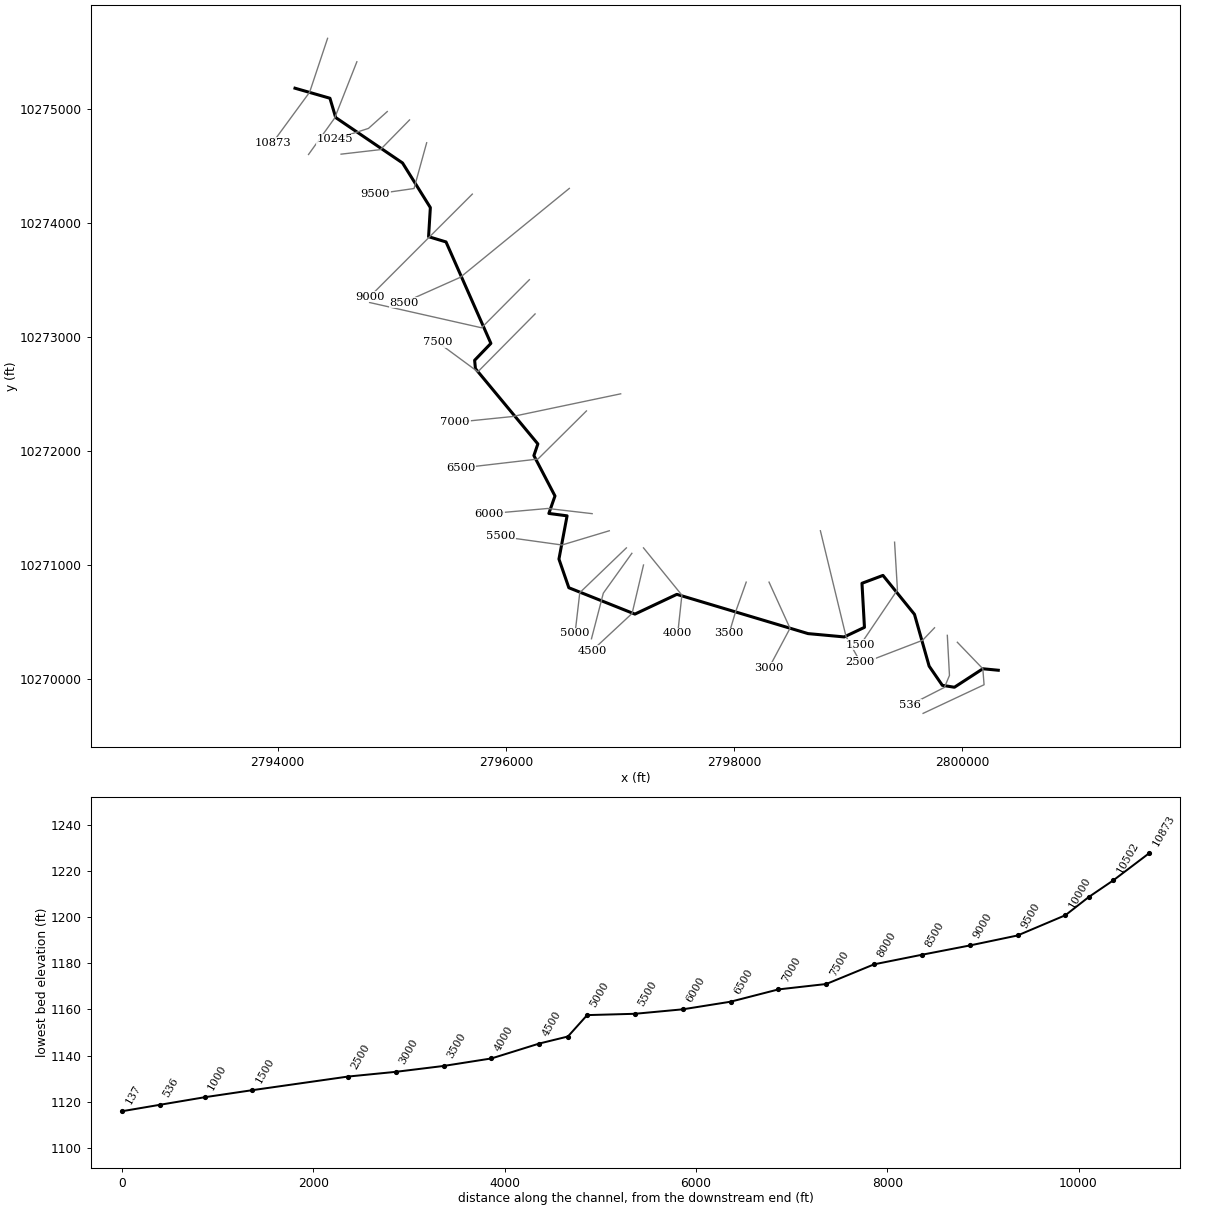
--- SANFERNANDO044.prj (project) ---

Proj Title=SANFERNANDO044 Base Level Engineering
Current Plan=p01
Default Exp/Contr=0.3,0.1
English Units
Geom File=g01
Flow File=f01
Plan File=p01
BEGIN DESCRIPTION:
SANFERNANDO044
END DESCRIPTION:

--- SANFERNANDO044.p01 (plan) ---

Plan Title=Multiple Run
Short Identifier=Multiple
Geom File=g01
Flow File=f01
Subcritical Flow
K Sum by GR= 0
Std Step Tol= 0.01
Critical Tol= 0.01
Num of Std Step Trials= 20
Max Error Tol= 0.3
Flow Tol Ratio= 0.001
Split Flow NTrial= 30
Split Flow Tol= 0.02
Split Flow Ratio= 0.02
Log Output Level= 0
Friction Slope Method= 1
Unsteady Friction Slope Method= 2
Unsteady Bridges Friction Slope Method= 1
Parabolic Critical Depth
Global Vel Dist=  1 , 1 , 1
Global Log Level= 0
CheckData=True
Encroach Param= -1, 0, 0, 0
BEGIN DESCRIPTION:
Multiple Run
END DESCRIPTION:

--- SANFERNANDO044.f01 (steady flow) ---

Flow Title=Multiple
Number of Profiles=7
Profile Names=10-year,25-year,50-year,1pct_min,100-year,1pct_plu,500-year
River Rch & RM= SANFERNANDO044,Reach-1,10873
     347     554     739     446     980    2150    1356
River Rch & RM= SANFERNANDO044,Reach-1,5000
     636    1049    1595    1019    2173    4635    2997
River Rch & RM= SANFERNANDO044,Reach-1,1500
     739    1234    1851    1077    2530    5947    3484
Boundary for River Rch & Prof#=SANFERNANDO044,Reach-1,1
Up Type=0
Dn Type=3
Dn Slope=0.005
Boundary for River Rch & Prof#=SANFERNANDO044,Reach-1,2
Up Type=0
Dn Type=3
Dn Slope=0.005
Boundary for River Rch & Prof#=SANFERNANDO044,Reach-1,3
Up Type=0
Dn Type=3
Dn Slope=0.005
Boundary for River Rch & Prof#=SANFERNANDO044,Reach-1,4
Up Type=0
Dn Type=3
Dn Slope=0.005
Boundary for River Rch & Prof#=SANFERNANDO044,Reach-1,5
Up Type=0
Dn Type=3
Dn Slope=0.005
Boundary for River Rch & Prof#=SANFERNANDO044,Reach-1,6
Up Type=0
Dn Type=3
Dn Slope=0.005
Boundary for River Rch & Prof#=SANFERNANDO044,Reach-1,7
Up Type=0
Dn Type=3
Dn Slope=0.005

--- SANFERNANDO044.g01 (geometry) ---

Geom Title=Existing Conditions

River Reach=SANFERNANDO044,Reach-1
Reach XY= 30
      2794152.00     10275181.00      2794458.25     10275093.00
      2794508.50     10274924.00      2795094.25     10274526.00
      2795338.00     10274135.00      2795322.50     10273880.00
      2795475.25     10273834.00      2795868.50     10272945.00
      2795726.00     10272797.00      2795733.00     10272724.00
      2796280.00     10272064.00      2796245.25     10271962.00
      2796430.00     10271608.00      2796376.50     10271455.00
      2796536.00     10271434.00      2796464.75     10271055.00
      2796551.50     10270804.00      2797130.50     10270573.00
      2797497.75     10270746.00      2798647.75     10270402.00
      2798964.75     10270373.00      2799141.75     10270457.00
      2799120.00     10270843.00      2799304.00     10270912.00
      2799580.00     10270571.00      2799708.50     10270117.00
      2799824.00     10269949.00      2799930.00     10269932.00
      2800179.00     10270094.00      2800314.50     10270081.00

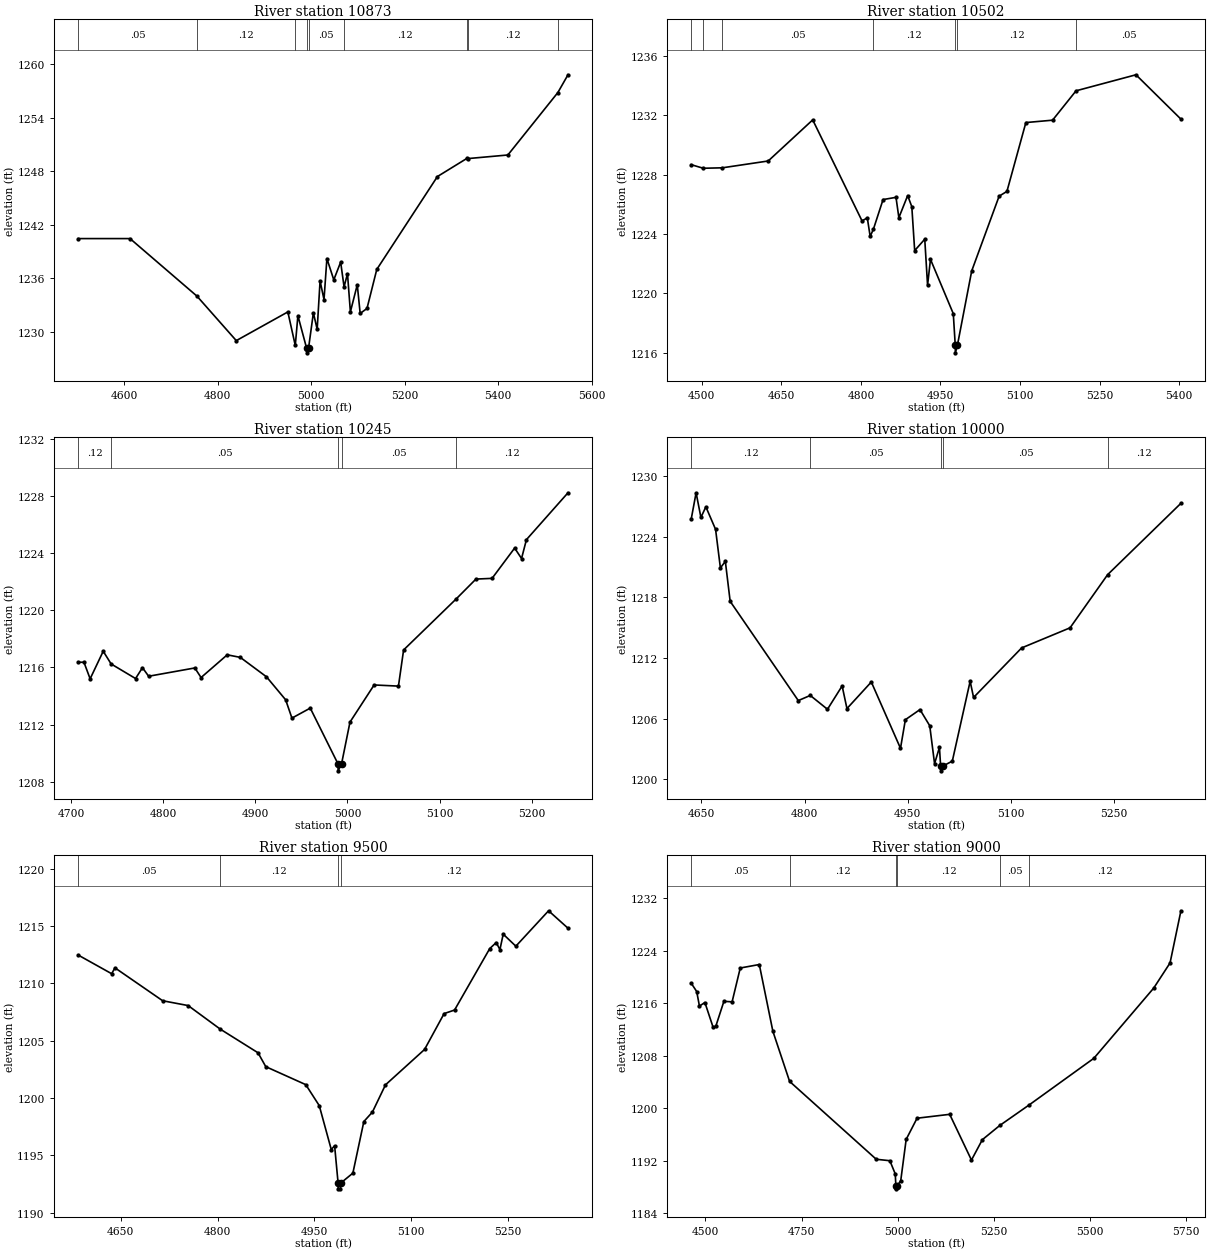
Type RM Length L Ch R = 1,10873,371,371,371
BEGIN DESCRIPTION:
SANFERNANDO044 22.0
END DESCRIPTION:
XS GIS Cut Line= 3
      2794437.53     10275617.98      2794280.25     10275146.00
      2793955.67     10274703.10
#Sta/Elev= 30
  4502.5 1240.46  4613.0 1240.46  4756.1 1234.00  4840.1 1229.01  4950.3 1232.23
  4966.2 1228.47  4971.8 1231.81  4990.5 1228.14  4990.8 1227.64  4994.5 1228.14
  5004.9 1232.13  5013.0 1230.28  5019.2 1235.71  5027.6 1233.62  5033.8 1238.22
  5048.5 1235.83  5063.2 1237.82  5070.5 1235.04  5077.8 1236.52  5084.0 1232.24
  5098.7 1235.28  5104.9 1232.06  5119.5 1232.62  5140.4 1237.00  5270.0 1247.42
  5332.8 1249.45  5335.8 1249.44  5420.6 1249.84  5527.5 1256.85  5549.1 1258.84
#Mann=9,-1,0
  4502.5    0.05       0  4756.1    0.12       0  4966.2    0.05       0
  4990.5    0.05       0  4994.5    0.05       0  5070.5    0.12       0
  5332.8    0.05       0  5335.8    0.12       0  5527.5    0.05       0
Bank Sta=4990.5,4994.5
Exp/Cntr=0.3,0.1

Type RM Length L Ch R = 1,10502,257,257,257
BEGIN DESCRIPTION:
Mapping XS 2fbe36d5
END DESCRIPTION:
XS GIS Cut Line= 3
      2794694.08     10275412.55      2794499.63     10274919.50
      2794270.55     10274600.18
#Sta/Elev= 30
  4480.3 1228.68  4502.9 1228.44  4538.8 1228.47  4625.3 1228.93  4709.2 1231.70
  4802.2 1224.89  4812.1 1225.10  4817.5 1223.85  4823.5 1224.32  4841.8 1226.33
  4866.2 1226.48  4871.6 1225.11  4888.2 1226.60  4896.0 1225.85  4901.4 1222.89
  4920.4 1223.66  4925.7 1220.56  4931.2 1222.30  4974.2 1218.64  4977.9 1216.50
  4978.1 1216.00  4981.9 1216.50  5008.9 1221.52  5060.6 1226.56  5075.3 1226.88
  5111.0 1231.52  5161.3 1231.68  5205.6 1233.66  5318.5 1234.74  5403.3 1231.75
#Mann=7,-1,0
  4480.3    0.05       0  4502.9    0.12       0  4538.8    0.05       0
  4823.5    0.12       0  4977.9    0.07       0  4981.9    0.12       0
  5205.6    0.05       0
Bank Sta=4977.9,4981.9
Exp/Cntr=0.3,0.1

Type RM Length L Ch R = 1,10245,245,245,245
BEGIN DESCRIPTION:
Mapping XS e214273b
END DESCRIPTION:
XS GIS Cut Line= 3
      2794960.56     10274976.32      2794795.64     10274828.76
      2794500.60     10274733.30
#Sta/Elev= 30
  4708.0 1216.36  4714.1 1216.36  4720.8 1215.20  4735.0 1217.13  4743.6 1216.24
  4770.1 1215.22  4777.6 1215.98  4784.3 1215.38  4834.4 1215.96  4841.2 1215.29
  4869.6 1216.88  4883.8 1216.70  4912.2 1215.34  4933.0 1213.73  4939.8 1212.45
  4959.7 1213.15  4989.7 1209.26  4990.0 1208.76  4993.7 1209.26  5002.8 1212.17
  5029.0 1214.77  5055.4 1214.69  5061.0 1217.22  5118.2 1220.80  5139.5 1222.18
  5157.0 1222.23  5181.5 1224.35  5189.0 1223.62  5194.3 1224.94  5239.4 1228.22
#Mann=5,-1,0
  4708.0    0.12       0  4743.6    0.05       0  4989.7    0.03       0
  4993.7    0.05       0  5118.2    0.12       0
Bank Sta=4989.7,4993.7
Exp/Cntr=0.3,0.1

Type RM Length L Ch R = 1,10000,500,500,500
BEGIN DESCRIPTION:
SANFERNANDO044 20.0
END DESCRIPTION:
XS GIS Cut Line= 3
      2795155.65     10274903.08      2794900.27     10274642.85
      2794555.66     10274603.11
#Sta/Elev= 30
  4635.4 1225.79  4642.4 1228.36  4649.4 1225.92  4656.6 1226.97  4670.7 1224.74
  4677.7 1220.93  4684.9 1221.57  4691.9 1217.62  4790.9 1207.80  4808.3 1208.31
  4833.3 1206.94  4854.6 1209.25  4861.6 1207.01  4897.0 1209.64  4939.4 1203.08
  4946.5 1205.91  4967.7 1206.91  4981.9 1205.31  4988.9 1201.56  4996.0 1203.17
  4997.7 1201.35  4998.0 1200.85  5001.7 1201.35  5014.7 1201.81  5040.6 1209.71
  5045.6 1208.11  5115.4 1213.01  5185.8 1215.00  5240.4 1220.26  5346.9 1227.32
#Mann=5,-1,0
  4635.4    0.12       0  4808.3    0.05       0  4997.7    0.03       0
  5001.7    0.05       0  5240.4    0.12       0
Bank Sta=4997.7,5001.7
Exp/Cntr=0.3,0.1

Type RM Length L Ch R = 1,9500,500,500,500
BEGIN DESCRIPTION:
SANFERNANDO044 19.0
END DESCRIPTION:
XS GIS Cut Line= 3
      2795305.69     10274703.12      2795195.15     10274302.17
      2794855.68     10274253.11
#Sta/Elev= 30
  4584.1 1212.46  4635.7 1210.84  4640.9 1211.35  4714.8 1208.48  4754.3 1208.06
  4803.9 1206.01  4862.6 1203.94  4874.6 1202.73  4936.6 1201.16  4957.5 1199.33
  4976.1 1195.50  4981.3 1195.83  4986.7 1192.57  4986.9 1192.07  4990.4 1192.07
  4990.7 1192.57  5009.6 1193.44  5026.6 1197.94  5039.9 1198.77  5060.1 1201.14
  5120.7 1204.23  5151.0 1207.36  5167.2 1207.67  5221.7 1213.03  5231.8 1213.56
  5237.5 1212.94  5242.6 1214.29  5262.2 1213.24  5312.9 1216.33  5343.0 1214.81
#Mann=4,-1,0
  4584.1    0.05       0  4803.9    0.12       0  4986.7    0.07       0
  4990.7    0.12       0
Bank Sta=4986.7,4990.7
Exp/Cntr=0.3,0.1

Type RM Length L Ch R = 1,9000,500,500,500
BEGIN DESCRIPTION:
SANFERNANDO044 18.0
END DESCRIPTION:
XS GIS Cut Line= 3
      2795705.68     10274253.11      2795325.90     10273873.60
      2794805.68     10273353.10
#Sta/Elev= 30
  4463.1 1219.01  4477.2 1217.76  4484.3 1215.55  4498.5 1216.09  4519.7 1212.34
  4526.7 1212.45  4547.9 1216.27  4569.2 1216.19  4590.4 1221.34  4639.9 1221.87
  4675.2 1211.71  4718.7 1204.08  4943.9 1192.23  4979.3 1192.01  4993.4 1189.99
  4994.8 1188.23  4995.1 1187.73  4998.8 1188.23  5007.6 1188.99  5021.7 1195.26
  5050.0 1198.48  5134.8 1199.07  5191.4 1192.11  5219.7 1195.21  5265.1 1197.38
  5342.1 1200.53  5509.6 1207.60  5665.2 1218.29  5707.6 1222.11  5735.9 1230.05
#Mann=6,-1,0
  4463.1    0.05       0  4718.7    0.12       0  4994.8    0.07       0
  4998.8    0.12       0  5265.1    0.05       0  5342.1    0.12       0
Bank Sta=4994.8,4998.8
Exp/Cntr=0.3,0.1

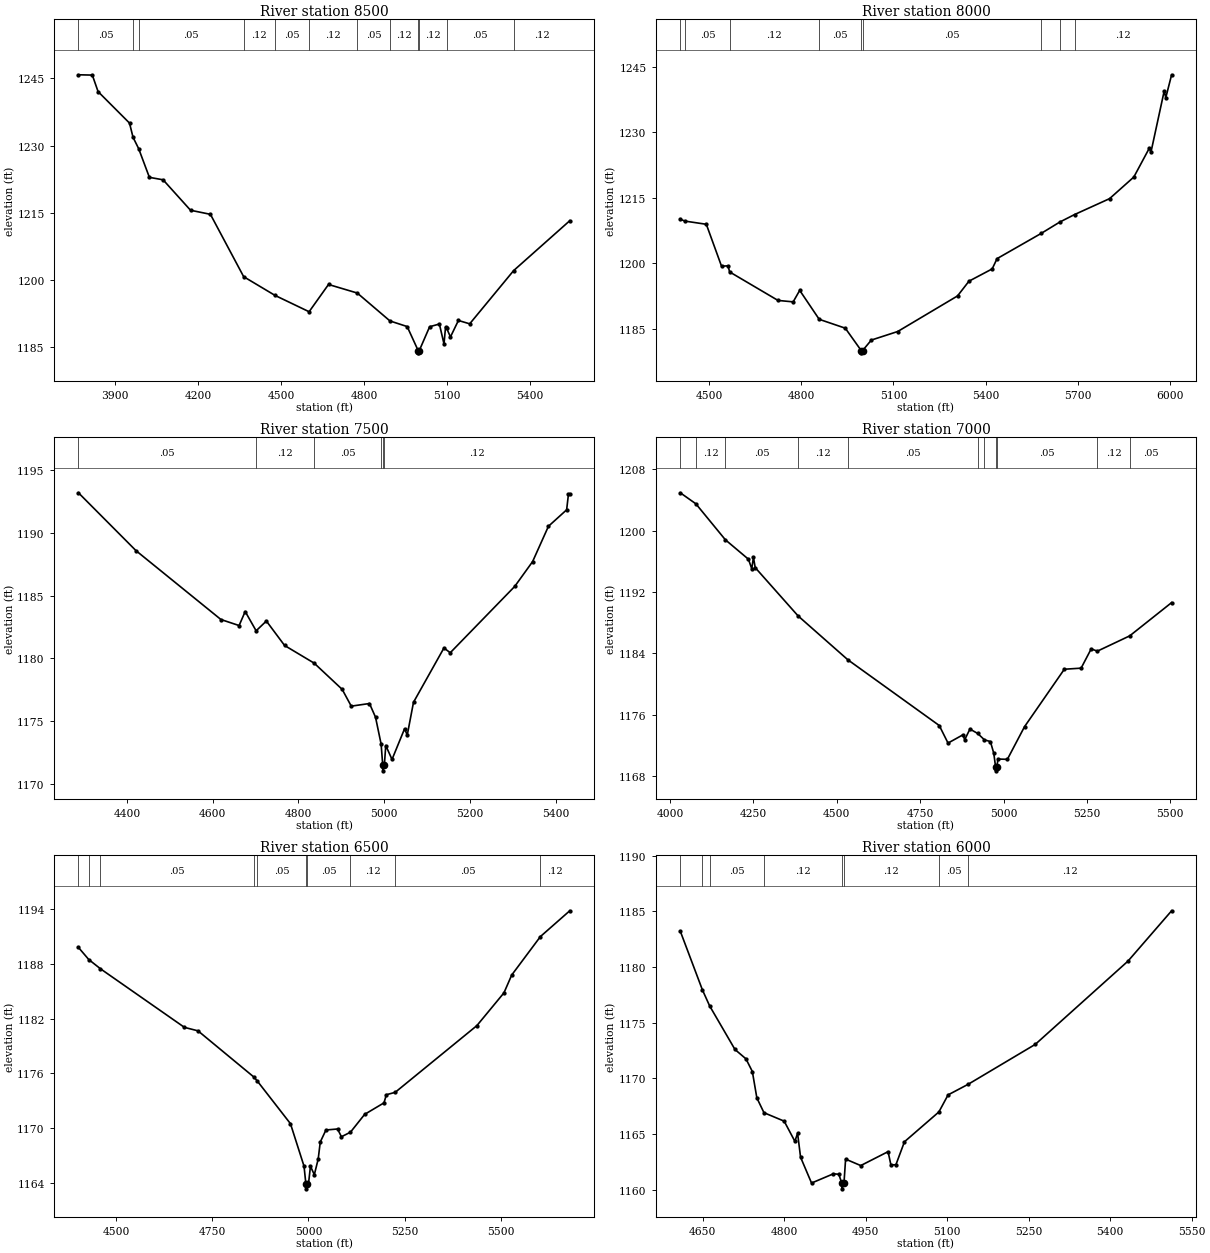
Type RM Length L Ch R = 1,8500,500,500,500
BEGIN DESCRIPTION:
SANFERNANDO044 17.0
END DESCRIPTION:
XS GIS Cut Line= 3
      2796555.65     10274303.08      2795601.04     10273524.27
      2795105.67     10273303.10
#Sta/Elev= 30
  3768.0 1245.82  3818.2 1245.75  3839.0 1242.06  3952.5 1235.03  3965.2 1231.86
  3985.5 1229.33  4024.3 1222.91  4073.8 1222.36  4172.9 1215.56  4244.7 1214.65
  4364.8 1200.72  4478.0 1196.54  4601.1 1192.89  4671.2 1198.98  4775.0 1197.07
  4893.2 1190.83  4955.3 1189.58  4995.0 1184.21  4995.2 1183.71  4999.0 1184.21
  5036.4 1189.54  5071.6 1190.15  5088.3 1185.69  5093.8 1189.43  5097.8 1189.20
  5111.6 1187.26  5140.3 1190.94  5181.1 1190.19  5339.8 1202.08  5542.5 1213.22
#Mann=12,-1,0
  3768.0    0.05       0  3965.2    0.12       0  3985.5    0.05       0
  4364.8    0.12       0  4478.0    0.05       0  4601.1    0.12       0
  4775.0    0.05       0  4893.2    0.12       0  4995.0    0.07       0
  4999.0    0.12       0  5097.8    0.05       0  5339.8    0.12       0
Bank Sta=4995,4999
Exp/Cntr=0.3,0.1

Type RM Length L Ch R = 1,8000,500,500,500
BEGIN DESCRIPTION:
SANFERNANDO044 16.0
END DESCRIPTION:
XS GIS Cut Line= 3
      2796205.65     10273503.08      2795786.71     10273081.70
      2794805.69     10273303.11
#Sta/Elev= 30
  4405.8 1210.10  4421.8 1209.69  4490.6 1208.97  4540.1 1199.39  4561.3 1199.46
  4566.5 1198.07  4724.0 1191.55  4773.4 1191.22  4794.7 1193.85  4858.2 1187.23
  4943.1 1185.20  4995.2 1180.06  4995.4 1179.56  4999.2 1180.06  5027.9 1182.48
  5113.8 1184.44  5308.6 1192.58  5345.8 1195.95  5421.4 1198.76  5437.3 1201.11
  5580.7 1206.87  5641.6 1209.48  5689.8 1211.20  5803.6 1214.83  5882.7 1219.78
  5933.2 1226.40  5938.3 1225.43  5981.5 1239.45  5986.7 1237.94  6005.7 1243.17
#Mann=9,-1,0
  4405.8    0.12       0  4421.8    0.05       0  4566.5    0.12       0
  4858.2    0.05       0  4995.2    0.05       0  4999.2    0.05       0
  5580.7    0.12       0  5641.6    0.05       0  5689.8    0.12       0
Bank Sta=4995.2,4999.2
Exp/Cntr=0.3,0.1

Type RM Length L Ch R = 1,7500,500,500,500
BEGIN DESCRIPTION:
SANFERNANDO044 15.0
END DESCRIPTION:
XS GIS Cut Line= 3
      2796255.71     10273203.14      2795754.33     10272696.20
      2795405.67     10272953.12
#Sta/Elev= 30
  4287.0 1193.21  4421.4 1188.59  4619.4 1183.10  4661.8 1182.62  4676.0 1183.74
  4701.5 1182.20  4725.4 1182.98  4767.9 1181.03  4836.9 1179.62  4902.2 1177.53
  4923.4 1176.19  4965.9 1176.40  4980.0 1175.31  4993.1 1173.16  4996.7 1171.53
  4996.9 1171.03  5000.7 1171.53  5003.9 1173.05  5018.5 1171.94  5047.8 1174.39
  5054.0 1173.88  5068.6 1176.50  5139.6 1180.83  5154.3 1180.45  5304.7 1185.74
  5346.4 1187.72  5383.4 1190.54  5425.8 1191.85  5430.0 1193.09  5433.1 1193.09
#Mann=6,-1,0
  4287.0    0.05       0  4701.5    0.12       0  4836.9    0.05       0
  4993.1    0.12       0  4996.7    0.07       0  5000.7    0.12       0
Bank Sta=4996.7,5000.7
Exp/Cntr=0.3,0.1

Type RM Length L Ch R = 1,7000,500,500,500
BEGIN DESCRIPTION:
SANFERNANDO044 14.0
END DESCRIPTION:
XS GIS Cut Line= 3
      2797005.64     10272503.10      2796057.10     10272304.09
      2795555.68     10272253.11
#Sta/Elev= 30
  4030.8 1204.95  4077.6 1203.51  4166.0 1198.82  4235.1 1196.29  4245.1 1195.05
  4250.2 1196.52  4255.5 1195.19  4384.1 1188.89  4533.3 1183.17  4807.3 1174.60
  4833.6 1172.31  4878.4 1173.39  4883.5 1172.74  4899.3 1174.14  4922.6 1173.56
  4942.8 1172.73  4960.6 1172.51  4970.8 1170.98  4976.2 1169.19  4976.4 1168.69
  4980.2 1169.19  4983.3 1170.23  5011.5 1170.19  5063.0 1174.45  5182.3 1181.94
  5232.6 1182.08  5262.8 1184.59  5281.5 1184.30  5378.3 1186.29  5504.0 1190.63
#Mann=11,-1,0
  4030.8    0.05       0  4077.6    0.12       0  4166.0    0.05       0
  4384.1    0.12       0  4533.3    0.05       0  4922.6    0.12       0
  4942.8    0.05       0  4976.2    0.05       0  4980.2    0.05       0
  5281.5    0.12       0  5378.3    0.05       0
Bank Sta=4976.2,4980.2
Exp/Cntr=0.3,0.1

Type RM Length L Ch R = 1,6500,500,500,500
BEGIN DESCRIPTION:
SANFERNANDO044 13.0
END DESCRIPTION:
XS GIS Cut Line= 3
      2796705.71     10272353.13      2796280.90     10271931.68
      2795605.65     10271853.11
#Sta/Elev= 30
  4401.6 1189.78  4428.6 1188.45  4459.0 1187.44  4677.4 1181.03  4712.7 1180.65
  4857.6 1175.61  4866.0 1175.21  4953.2 1170.49  4988.5 1165.84  4993.4 1163.86
  4993.7 1163.36  4997.4 1163.86  5000.0 1163.86  5005.2 1165.83  5015.3 1164.91
  5025.4 1166.63  5030.7 1168.48  5045.5 1169.80  5075.7 1169.91  5085.8 1169.06
  5109.3 1169.56  5146.2 1171.51  5196.5 1172.77  5202.7 1173.66  5225.6 1173.92
  5438.1 1181.22  5508.6 1184.81  5528.8 1186.76  5603.5 1190.97  5679.8 1193.79
#Mann=10,-1,0
  4401.6    0.05       0  4428.6    0.12       0  4459.0    0.05       0
  4857.6    0.12       0  4866.0    0.05       0  4993.4    0.03       0
  4997.4    0.05       0  5109.3    0.12       0  5225.6    0.05       0
  5603.5    0.12       0
Bank Sta=4993.4,4997.4
Exp/Cntr=0.3,0.1

Type RM Length L Ch R = 1,6000,500,500,500
BEGIN DESCRIPTION:
SANFERNANDO044 12.0
END DESCRIPTION:
XS GIS Cut Line= 3
      2796755.73     10271453.11      2796366.77     10271498.54
      2795855.69     10271453.11
#Sta/Elev= 30
  4608.4 1183.21  4649.1 1177.94  4662.5 1176.49  4709.1 1172.58  4729.3 1171.74
  4741.1 1170.60  4749.4 1168.23  4762.5 1166.90  4799.7 1166.14  4819.4 1164.33
  4824.4 1165.05  4829.9 1162.90  4850.1 1160.58  4890.3 1161.41  4900.4 1161.37
  4905.8 1160.56  4906.0 1160.06  4909.8 1160.56  4912.8 1162.73  4940.7 1162.15
  4991.0 1163.40  4996.2 1162.22  5005.4 1162.22  5021.2 1164.29  5084.6 1166.97
  5101.5 1168.50  5138.4 1169.45  5262.1 1173.04  5432.8 1180.52  5513.1 1185.04
#Mann=8,-1,0
  4608.4    0.05       0  4649.1    0.12       0  4662.5    0.05       0
  4762.5    0.12       0  4905.8    0.07       0  4909.8    0.12       0
  5084.6    0.05       0  5138.4    0.12       0
Bank Sta=4905.8,4909.8
Exp/Cntr=0.3,0.1

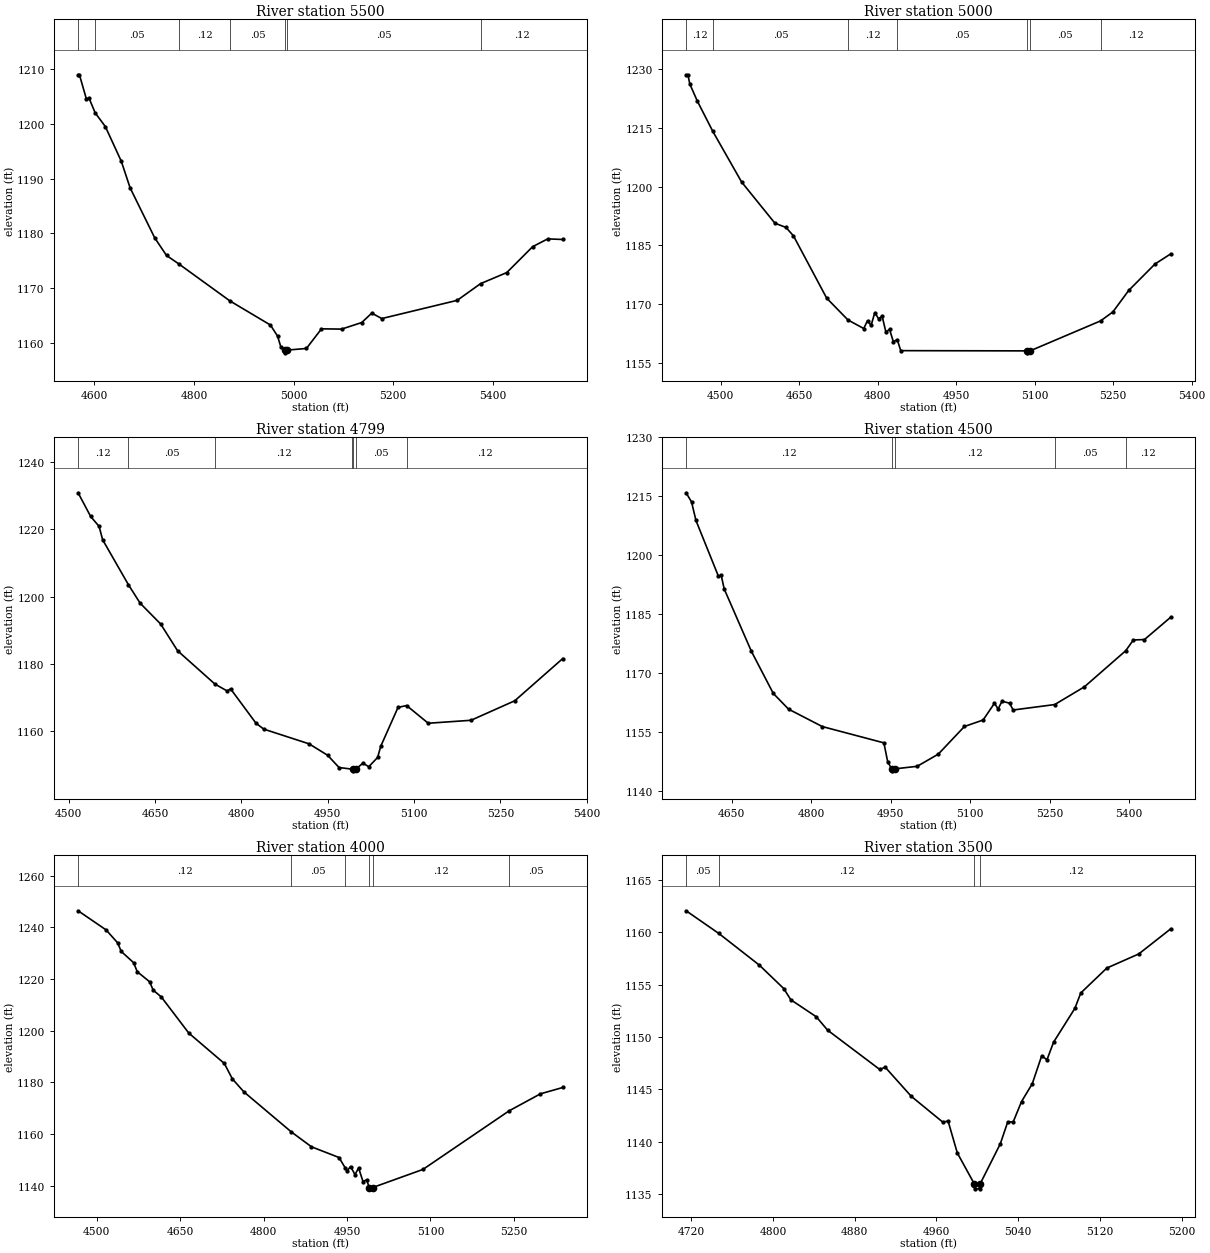
Type RM Length L Ch R = 1,5500,500,500,500
BEGIN DESCRIPTION:
SANFERNANDO044 11.0
END DESCRIPTION:
XS GIS Cut Line= 3
      2796905.73     10271303.12      2796491.37     10271178.48
      2795955.64     10271253.12
#Sta/Elev= 30
  4567.3 1208.97  4570.0 1208.97  4583.9 1204.56  4589.1 1204.74  4601.6 1202.01
  4622.1 1199.49  4654.1 1193.15  4671.8 1188.29  4721.2 1179.15  4744.9 1175.93
  4770.4 1174.33  4872.2 1167.62  4953.7 1163.20  4968.0 1161.17  4974.6 1159.19
  4983.1 1158.62  4983.3 1158.12  4987.1 1158.62  5025.9 1158.92  5056.2 1162.51
  5096.6 1162.46  5137.0 1163.66  5157.2 1165.38  5177.4 1164.39  5328.8 1167.72
  5375.7 1170.77  5428.4 1172.80  5480.3 1177.53  5510.6 1178.96  5540.9 1178.85
#Mann=7,-1,0
  4567.3    0.12       0  4601.6    0.05       0  4770.4    0.12       0
  4872.2    0.05       0  4983.1    0.03       0  4987.1    0.05       0
  5375.7    0.12       0
Bank Sta=4983.1,4987.1
Exp/Cntr=0.3,0.1

Type RM Length L Ch R = 1,5000,201,201,201
BEGIN DESCRIPTION:
SANFERNANDO044 10.0
END DESCRIPTION:
XS GIS Cut Line= 3
      2797055.68     10271153.11      2796647.38     10270760.69
      2796605.68     10270403.12
#Sta/Elev= 30
  4433.7 1228.55  4437.2 1228.55  4440.8 1226.20  4454.9 1221.91  4484.8 1214.09
  4539.8 1201.17  4603.4 1190.66  4624.7 1189.56  4638.9 1187.42  4702.4 1171.51
  4743.1 1165.94  4773.2 1163.76  4780.4 1165.76  4787.3 1164.56  4794.3 1167.81
  4801.5 1166.27  4808.4 1166.89  4815.6 1162.82  4822.5 1163.57  4829.8 1160.38
  4837.2 1160.94  4843.9 1158.11  5085.4 1158.05  5085.8 1157.55  5091.0 1158.05
  5225.7 1165.70  5249.3 1167.99  5279.5 1173.47  5329.8 1180.23  5360.0 1182.83
#Mann=7,-1,0
  4433.7    0.12       0  4484.8    0.05       0  4743.1    0.12       0
  4837.2    0.05       0  5085.4    0.03       0  5091.0    0.05       0
  5225.7    0.12       0
Bank Sta=5085.4,5091
Exp/Cntr=0.3,0.1

Type RM Length L Ch R = 1,4799,299,299,299
BEGIN DESCRIPTION:
Mapping XS 56019c85
END DESCRIPTION:
XS GIS Cut Line= 3
      2797103.60     10271105.48      2796853.62     10270756.53
      2796749.80     10270356.85
#Sta/Elev= 30
  4516.1 1230.83  4537.9 1223.81  4552.6 1220.85  4558.8 1216.86  4603.6 1203.52
  4623.9 1198.05  4659.5 1191.88  4688.9 1183.94  4753.7 1174.06  4774.9 1172.00
  4781.1 1172.61  4825.3 1162.39  4838.8 1160.65  4917.4 1156.29  4949.7 1152.89
  4969.5 1149.26  4992.3 1148.77  4993.2 1148.77  4993.7 1148.27  4998.9 1148.77
  5010.9 1150.56  5021.2 1149.50  5036.6 1152.26  5041.9 1155.53  5072.0 1167.10
  5086.9 1167.66  5124.5 1162.40  5198.8 1163.28  5274.8 1169.07  5358.3 1181.62
#Mann=7,-1,0
  4516.1    0.12       0  4603.6    0.05       0  4753.7    0.12       0
  4992.3    0.05       0  4993.2    0.03       0  4998.9    0.05       0
  5086.9    0.12       0
Bank Sta=4993.2,4998.9
Exp/Cntr=0.3,0.1

Type RM Length L Ch R = 1,4500,500,500,500
BEGIN DESCRIPTION:
SANFERNANDO044 9.0
END DESCRIPTION:
XS GIS Cut Line= 3
      2797205.69     10271003.13      2797105.83     10270578.92
      2796755.68     10270253.10
#Sta/Elev= 30
  4564.2 1215.89  4574.5 1213.56  4582.8 1208.86  4625.2 1194.67  4630.3 1194.98
  4636.1 1191.44  4687.5 1175.56  4728.6 1164.91  4757.4 1160.91  4821.1 1156.48
  4937.2 1152.34  4944.3 1147.60  4951.7 1145.73  4952.2 1145.23  4957.6 1145.73
  5000.0 1146.38  5039.8 1149.47  5089.1 1156.50  5124.3 1158.14  5145.8 1162.41
  5152.6 1160.95  5160.0 1162.92  5174.2 1162.42  5181.0 1160.69  5259.3 1162.07
  5315.3 1166.57  5393.2 1175.74  5407.7 1178.48  5428.7 1178.60  5478.3 1184.29
#Mann=5,-1,0
  4564.2    0.12       0  4951.7    0.07       0  4957.6    0.12       0
  5259.3    0.05       0  5393.2    0.12       0
Bank Sta=4951.7,4957.6
Exp/Cntr=0.3,0.1

Type RM Length L Ch R = 1,4000,500,500,500
BEGIN DESCRIPTION:
SANFERNANDO044 8.0
END DESCRIPTION:
XS GIS Cut Line= 3
      2797205.67     10271153.13      2797542.02     10270739.14
      2797505.68     10270403.10
#Sta/Elev= 30
  4466.6 1246.45  4516.9 1239.05  4537.7 1234.04  4544.2 1230.70  4566.5 1226.33
  4572.9 1222.87  4595.2 1218.96  4601.7 1215.68  4616.0 1213.14  4665.6 1199.09
  4729.5 1187.33  4743.9 1181.37  4764.7 1176.31  4849.7 1160.86  4886.1 1155.06
  4935.7 1150.90  4946.6 1146.96  4950.0 1145.71  4956.5 1147.42  4964.4 1144.27
  4970.9 1146.85  4978.8 1141.60  4985.2 1142.26  4990.2 1139.27  4990.7 1138.77
  4996.1 1139.27  5086.5 1146.28  5241.6 1168.99  5297.8 1175.56  5338.0 1178.02
#Mann=6,-1,0
  4466.6    0.12       0  4849.7    0.05       0  4946.6    0.12       0
  4990.2    0.07       0  4996.1    0.12       0  5241.6    0.05       0
Bank Sta=4990.2,4996.1
Exp/Cntr=0.3,0.1

Type RM Length L Ch R = 1,3500,500,500,500
BEGIN DESCRIPTION:
SANFERNANDO044 7.0
END DESCRIPTION:
XS GIS Cut Line= 3
      2798105.69     10270853.13      2798009.86     10270584.72
      2797955.69     10270403.13
#Sta/Elev= 30
  4715.0 1162.07  4747.1 1159.90  4786.7 1156.88  4810.6 1154.64  4817.5 1153.57
  4842.4 1151.95  4853.6 1150.66  4904.6 1146.91  4909.9 1147.13  4935.4 1144.35
  4966.2 1141.89  4971.5 1141.98  4980.5 1138.94  4997.0 1136.01  4997.5 1135.51
  5002.5 1135.51  5003.0 1136.01  5022.6 1139.81  5029.9 1141.91  5035.2 1141.90
  5043.4 1143.85  5053.9 1145.55  5063.1 1148.21  5068.3 1147.84  5074.7 1149.51
  5095.6 1152.75  5101.4 1154.22  5126.9 1156.60  5158.2 1157.95  5189.5 1160.35
#Mann=4,-1,0
  4715.0    0.05       0  4747.1    0.12       0  4997.0    0.07       0
  5003.0    0.12       0
Bank Sta=4997,5003
Exp/Cntr=0.3,0.1

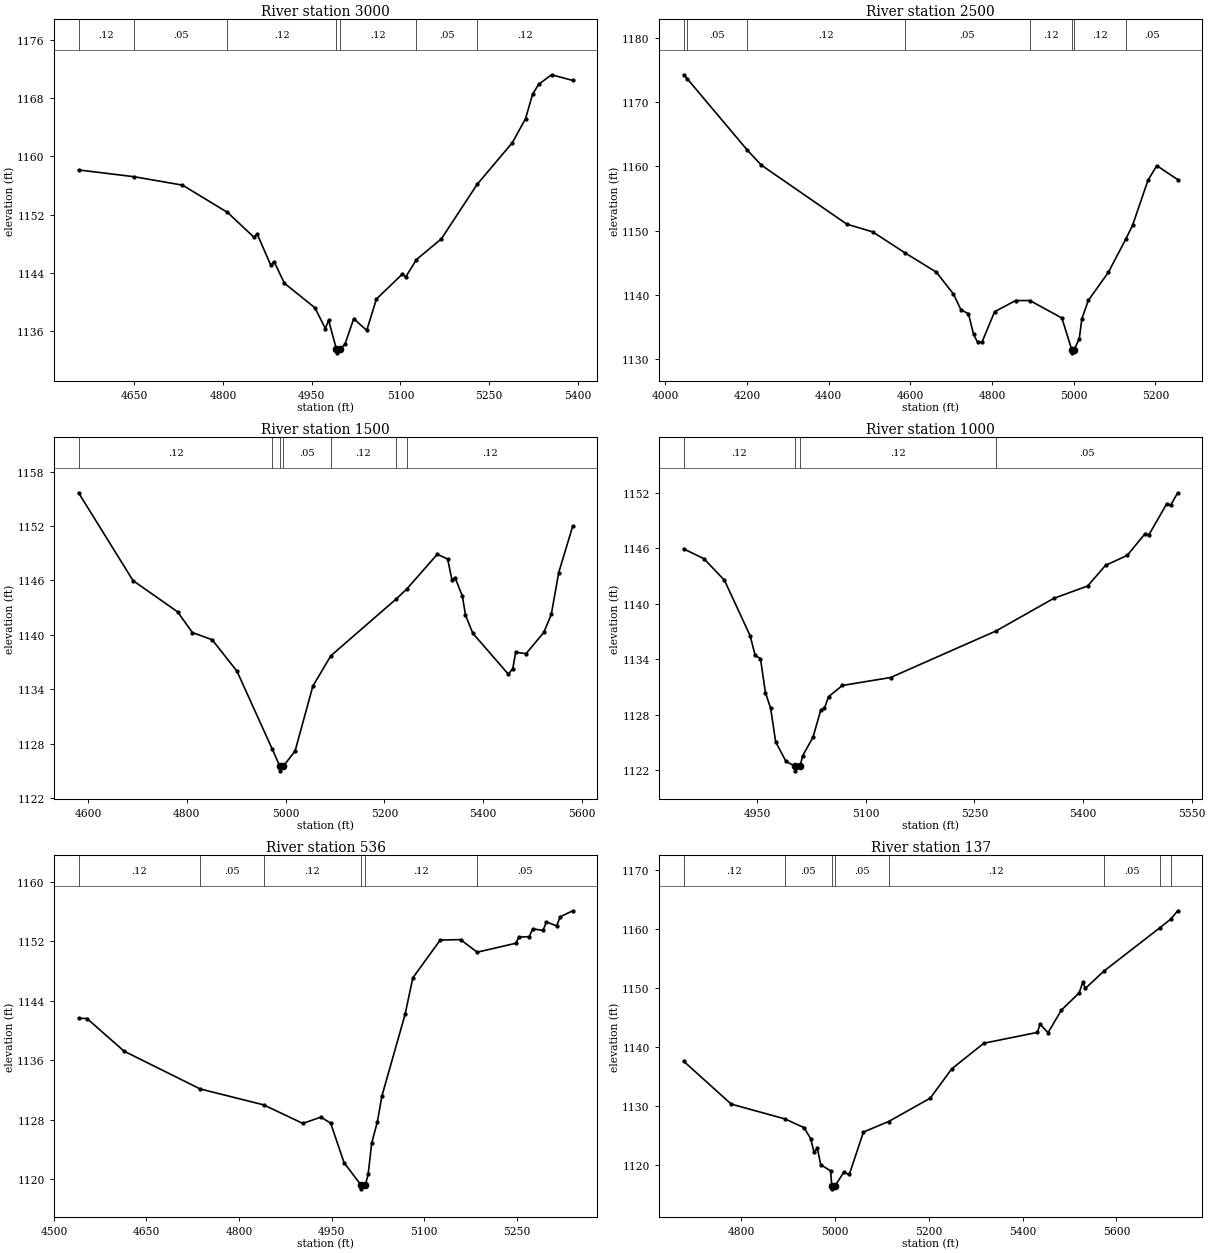
Type RM Length L Ch R = 1,3000,500,500,500
BEGIN DESCRIPTION:
SANFERNANDO044 6.0
END DESCRIPTION:
XS GIS Cut Line= 3
      2798305.68     10270853.13      2798489.60     10270448.68
      2798305.67     10270103.08
#Sta/Elev= 30
  4555.7 1158.14  4649.3 1157.21  4731.4 1156.05  4807.5 1152.30  4852.3 1148.88
  4857.7 1149.34  4880.8 1145.02  4886.3 1145.52  4903.9 1142.54  4955.5 1139.16
  4973.1 1136.30  4978.6 1137.44  4991.8 1133.46  4992.3 1132.96  4997.8 1133.46
  5006.3 1134.16  5021.1 1137.66  5043.1 1136.05  5059.4 1140.36  5103.4 1143.81
  5109.0 1143.41  5127.2 1145.80  5169.3 1148.65  5229.8 1156.15  5289.5 1161.91
  5311.7 1165.21  5323.5 1168.54  5333.7 1169.92  5355.7 1171.24  5391.5 1170.46
#Mann=7,-1,0
  4555.7    0.12       0  4649.3    0.05       0  4807.5    0.12       0
  4991.8    0.07       0  4997.8    0.12       0  5127.2    0.05       0
  5229.8    0.12       0
Bank Sta=4991.8,4997.8
Exp/Cntr=0.3,0.1

Type RM Length L Ch R = 1,2500,1000,1000,1000
BEGIN DESCRIPTION:
SANFERNANDO044 5.0
END DESCRIPTION:
XS GIS Cut Line= 3
      2798755.68     10271303.14      2798980.77     10270374.94
      2799105.69     10270153.10
#Sta/Elev= 30
  4044.9 1174.31  4053.8 1173.70  4201.3 1162.53  4235.6 1160.20  4444.6 1150.99
  4508.0 1149.79  4585.9 1146.56  4663.8 1143.50  4705.6 1140.09  4724.1 1137.61
  4742.3 1137.02  4754.9 1133.78  4765.2 1132.53  4775.5 1132.59  4806.4 1137.33
  4857.8 1139.07  4892.7 1139.07  4971.0 1136.35  4995.1 1131.41  4995.6 1130.91
  5001.2 1131.41  5013.6 1133.12  5019.8 1136.18  5035.7 1139.09  5084.8 1143.47
  5127.4 1148.66  5144.0 1150.80  5181.6 1157.81  5203.3 1160.13  5254.6 1157.95
#Mann=8,-1,0
  4044.9    0.12       0  4053.8    0.05       0  4201.3    0.12       0
  4585.9    0.05       0  4892.7    0.12       0  4995.1    0.07       0
  5001.2    0.12       0  5127.4    0.05       0
Bank Sta=4995.1,5001.2
Exp/Cntr=0.3,0.1

Type RM Length L Ch R = 1,1500,500,500,500
BEGIN DESCRIPTION:
SANFERNANDO044 3.0
END DESCRIPTION:
XS GIS Cut Line= 3
      2799405.69     10271203.07      2799430.81     10270784.92
      2799105.71     10270303.15
#Sta/Elev= 30
  4581.1 1155.66  4691.3 1145.98  4781.4 1142.54  4811.5 1140.25  4851.5 1139.46
  4901.6 1136.00  4973.3 1127.38  4988.4 1125.51  4988.9 1125.01  4995.2 1125.51
  5019.2 1127.18  5055.2 1134.34  5091.6 1137.69  5223.6 1143.94  5244.8 1145.02
  5307.0 1148.88  5328.0 1148.36  5336.9 1146.02  5342.9 1146.32  5357.9 1144.26
  5364.1 1142.18  5378.9 1140.18  5450.9 1135.66  5459.8 1136.28  5465.8 1138.08
  5486.8 1137.93  5522.8 1140.28  5537.8 1142.26  5552.8 1146.86  5581.2 1151.99
#Mann=7,-1,0
  4581.1    0.12       0  4973.3    0.05       0  4988.4    0.05       0
  4995.2    0.05       0  5091.6    0.12       0  5223.6    0.05       0
  5244.8    0.12       0
Bank Sta=4988.4,4995.2
Exp/Cntr=0.3,0.1

Type RM Length L Ch R = 1,1000,464,464,464
BEGIN DESCRIPTION:
SANFERNANDO044 2.0
END DESCRIPTION:
XS GIS Cut Line= 3
      2799755.69     10270453.12      2799651.13     10270343.50
      2799155.65     10270153.10
#Sta/Elev= 30
  4848.5 1145.92  4876.7 1144.85  4905.0 1142.52  4940.5 1136.52  4947.4 1134.41
  4954.7 1134.06  4961.6 1130.38  4968.8 1128.69  4975.7 1125.07  4989.9 1122.96
  5002.4 1122.44  5002.9 1121.94  5009.3 1122.44  5013.1 1123.59  5027.3 1125.58
  5037.8 1128.46  5043.1 1128.71  5048.7 1129.95  5067.8 1131.16  5134.4 1132.02
  5280.3 1137.06  5359.4 1140.56  5406.4 1141.90  5431.1 1144.13  5461.1 1145.21
  5485.8 1147.56  5491.1 1147.44  5515.8 1150.81  5521.1 1150.63  5530.8 1151.97
#Mann=4,-1,0
  4848.5    0.12       0  5002.4    0.07       0  5009.3    0.12       0
  5280.3    0.05       0
Bank Sta=5002.4,5009.3
Exp/Cntr=0.3,0.1

Type RM Length L Ch R = 1,536,399,399,399
BEGIN DESCRIPTION:
Mapping XS 75b0adba
END DESCRIPTION:
XS GIS Cut Line= 4
      2799867.79     10270386.81      2799886.61     10270035.50
      2799842.70     10269930.94      2799543.63     10269778.27
#Sta/Elev= 30
  4540.0 1141.64  4553.7 1141.60  4613.8 1137.21  4737.1 1132.13  4839.9 1129.99
  4903.5 1127.49  4932.7 1128.34  4948.6 1127.53  4970.3 1122.22  4997.8 1119.19
  4998.3 1118.69  5004.8 1119.19  5009.5 1120.71  5015.1 1124.84  5024.3 1127.70
  5031.7 1131.18  5069.2 1142.15  5081.8 1147.08  5126.2 1152.16  5159.1 1152.22
  5186.1 1150.53  5248.3 1151.72  5253.9 1152.56  5270.5 1152.62  5276.2 1153.67
  5292.8 1153.46  5298.4 1154.60  5315.0 1154.06  5320.6 1155.29  5341.0 1156.10
#Mann=6,-1,0
  4540.0    0.12       0  4737.1    0.05       0  4839.9    0.12       0
  4997.8    0.07       0  5004.8    0.12       0  5186.1    0.05       0
Bank Sta=4997.8,5004.8
Exp/Cntr=0.3,0.1

Type RM Length L Ch R = 1,137,0,0,0
BEGIN DESCRIPTION:
SANFERNANDO044 1.0
END DESCRIPTION:
XS GIS Cut Line= 4
      2799955.62     10270326.19      2800179.00     10270094.00
      2800189.84     10269953.94      2799655.68     10269703.11
#Sta/Elev= 30
  4677.8 1137.55  4779.2 1130.26  4893.8 1127.74  4934.5 1126.26  4948.7 1124.39
  4955.9 1122.06  4962.8 1122.81  4970.1 1119.96  4991.2 1118.93  4993.6 1116.38
  4994.1 1115.88  5000.6 1116.38  5018.9 1118.66  5031.0 1118.34  5061.1 1125.52
  5114.7 1127.30  5203.5 1131.27  5249.2 1136.24  5317.6 1140.58  5431.7 1142.42
  5437.2 1143.81  5454.4 1142.38  5482.8 1146.20  5520.7 1149.13  5528.4 1150.94
  5533.9 1149.89  5573.3 1152.81  5692.1 1160.14  5715.5 1161.62  5730.6 1163.05
#Mann=8,-1,0
  4677.8    0.12       0  4893.8    0.05       0  4993.6    0.05       0
  5000.6    0.05       0  5114.7    0.12       0  5573.3    0.05       0
  5692.1    0.12       0  5715.5    0.05       0
Bank Sta=4993.6,5000.6
Exp/Cntr=0.3,0.1

Chan Stop Cuts=-1