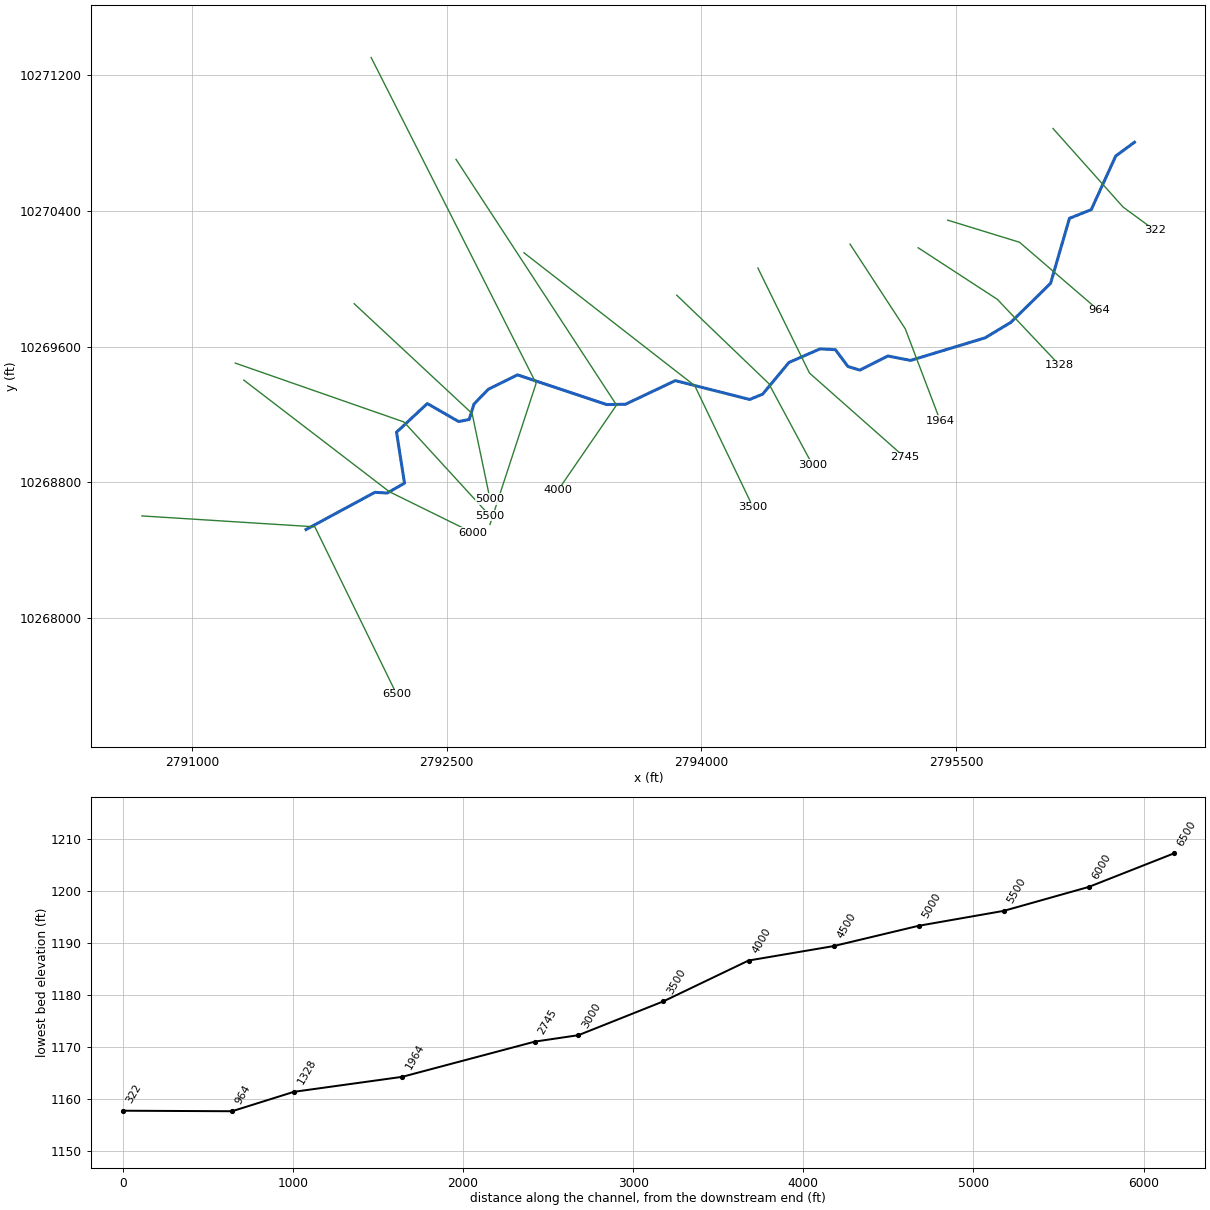
--- SANFERNANDO045.prj (project) ---

Proj Title=SANFERNANDO045 Base Level Engineering
Current Plan=p01
Default Exp/Contr=0.3,0.1
English Units
Geom File=g01
Flow File=f01
Plan File=p01
BEGIN DESCRIPTION:
SANFERNANDO045
END DESCRIPTION:

--- SANFERNANDO045.p01 (plan) ---

Plan Title=Multiple Run
Short Identifier=Multiple
Geom File=g01
Flow File=f01
Subcritical Flow
K Sum by GR= 0
Std Step Tol= 0.01
Critical Tol= 0.01
Num of Std Step Trials= 20
Max Error Tol= 0.3
Flow Tol Ratio= 0.001
Split Flow NTrial= 30
Split Flow Tol= 0.02
Split Flow Ratio= 0.02
Log Output Level= 0
Friction Slope Method= 1
Unsteady Friction Slope Method= 2
Unsteady Bridges Friction Slope Method= 1
Parabolic Critical Depth
Global Vel Dist=  1 , 1 , 1
Global Log Level= 0
CheckData=True
Encroach Param= -1, 0, 0, 0
BEGIN DESCRIPTION:
Multiple Run
END DESCRIPTION:

--- SANFERNANDO045.f01 (steady flow) ---

Flow Title=Multiple
Number of Profiles=7
Profile Names=10-year,25-year,50-year,1pct_min,100-year,1pct_plu,500-year
River Rch & RM= SANFERNANDO045,Reach-1,6500
     296     467     507     298     652    1425     879
River Rch & RM= SANFERNANDO045,Reach-1,322
     403     646     753     420     979    2286    1312
Boundary for River Rch & Prof#=SANFERNANDO045,Reach-1,1
Up Type=0
Dn Type=3
Dn Slope=0.005
Boundary for River Rch & Prof#=SANFERNANDO045,Reach-1,2
Up Type=0
Dn Type=3
Dn Slope=0.005
Boundary for River Rch & Prof#=SANFERNANDO045,Reach-1,3
Up Type=0
Dn Type=3
Dn Slope=0.005
Boundary for River Rch & Prof#=SANFERNANDO045,Reach-1,4
Up Type=0
Dn Type=3
Dn Slope=0.005
Boundary for River Rch & Prof#=SANFERNANDO045,Reach-1,5
Up Type=0
Dn Type=3
Dn Slope=0.005
Boundary for River Rch & Prof#=SANFERNANDO045,Reach-1,6
Up Type=0
Dn Type=3
Dn Slope=0.005
Boundary for River Rch & Prof#=SANFERNANDO045,Reach-1,7
Up Type=0
Dn Type=3
Dn Slope=0.005

--- SANFERNANDO045.g01 (geometry) ---

Geom Title=Existing Conditions

River Reach=SANFERNANDO045,Reach-1
Reach XY= 30
      2791672.25     10268523.00      2792077.50     10268742.00
      2792150.25     10268738.00      2792252.25     10268796.00
      2792205.25     10269096.00      2792386.50     10269265.00
      2792570.75     10269159.00      2792633.25     10269171.00
      2792661.50     10269262.00      2792745.75     10269349.00
      2792917.75     10269434.00      2793442.75     10269259.00
      2793554.00     10269261.00      2793847.50     10269400.00
      2794285.00     10269289.00      2794361.25     10269320.00
      2794516.50     10269507.00      2794699.75     10269587.00
      2794790.25     10269582.00      2794864.00     10269483.00
      2794934.25     10269462.00      2795099.25     10269545.00
      2795232.75     10269519.00      2795672.00     10269652.00
      2795823.25     10269743.00      2796057.50     10269973.00
      2796168.75     10270356.00      2796297.00     10270407.00
      2796441.25     10270723.00      2796551.50     10270804.00

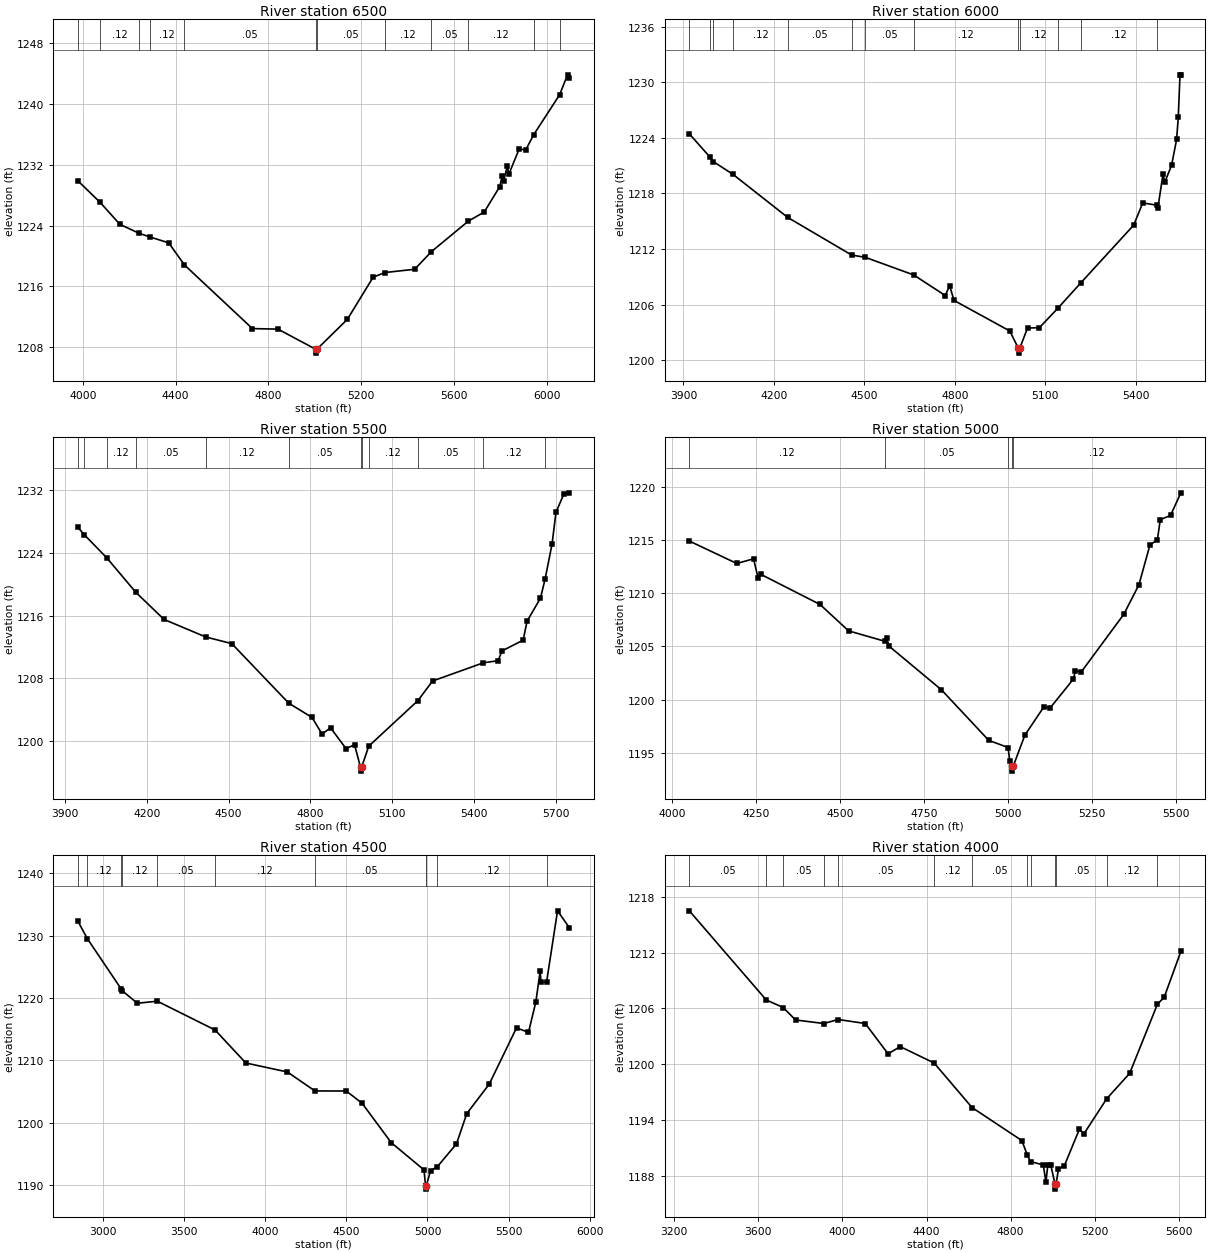
Type RM Length L Ch R = 1,6500,500,500,500
BEGIN DESCRIPTION:
SANFERNANDO045 13.0
END DESCRIPTION:
XS GIS Cut Line= 3
      2790705.69     10268603.11      2791724.07     10268538.91
      2792205.71     10267553.07
#Sta/Elev= 30
  3979.6 1229.87  4074.9 1227.05  4159.9 1224.16  4241.9 1222.99  4287.7 1222.51
  4370.4 1221.72  4438.3 1218.81  4731.1 1210.43  4841.3 1210.36  5004.4 1207.70
  5004.7 1207.20  5008.4 1207.70  5140.0 1211.64  5251.3 1217.20  5301.6 1217.81
  5430.0 1218.24  5502.6 1220.57  5661.0 1224.57  5729.9 1225.78  5796.7 1229.12
  5807.3 1230.55  5812.9 1229.82  5829.8 1231.87  5835.4 1230.72  5880.4 1234.08
  5908.5 1233.95  5943.5 1235.98  6054.9 1241.23  6088.7 1243.84  6097.2 1243.45
#Mann=12,-1,0
  3979.6    0.05       0  4074.9    0.12       0  4241.9    0.05       0
  4287.7    0.12       0  4438.3    0.05       0  5004.4    0.05       0
  5008.4    0.05       0  5301.6    0.12       0  5502.6    0.05       0
  5661.0    0.12       0  5943.5    0.05       0  6054.9    0.12       0
Bank Sta=5004.4,5008.4
Exp/Cntr=0.3,0.1

Type RM Length L Ch R = 1,6000,500,500,500
BEGIN DESCRIPTION:
SANFERNANDO045 12.0
END DESCRIPTION:
XS GIS Cut Line= 3
      2791305.71     10269403.09      2792163.16     10268745.62
      2792655.69     10268503.11
#Sta/Elev= 30
  3919.5 1224.43  3988.3 1221.90  3999.1 1221.43  4064.3 1220.05  4245.8 1215.40
  4457.7 1211.34  4503.3 1211.09  4663.4 1209.19  4767.9 1206.97  4782.5 1208.03
  4797.0 1206.44  4981.9 1203.14  5010.7 1201.25  5010.9 1200.75  5014.7 1201.25
  5040.7 1203.46  5080.1 1203.50  5141.7 1205.61  5218.0 1208.36  5392.9 1214.58
  5422.6 1216.97  5470.1 1216.72  5473.1 1216.47  5490.0 1220.11  5495.6 1219.19
  5518.1 1221.01  5535.0 1223.82  5540.5 1226.22  5546.2 1230.80  5549.0 1230.80
#Mann=13,-1,0
  3919.5    0.05       0  3988.3    0.12       0  3999.1    0.05       0
  4064.3    0.12       0  4245.8    0.05       0  4457.7    0.12       0
  4503.3    0.05       0  4663.4    0.12       0  5010.7    0.07       0
  5014.7    0.12       0  5141.7    0.05       0  5218.0    0.12       0
  5470.1    0.05       0
Bank Sta=5010.7,5014.7
Exp/Cntr=0.3,0.1

Type RM Length L Ch R = 1,5500,500,500,500
BEGIN DESCRIPTION:
SANFERNANDO045 11.0
END DESCRIPTION:
XS GIS Cut Line= 3
      2791255.64     10269503.13      2792249.16     10269156.34
      2792755.69     10268603.10
#Sta/Elev= 30
  3947.7 1227.24  3970.0 1226.34  4053.6 1223.35  4159.8 1218.96  4263.3 1215.50
  4415.7 1213.27  4511.8 1212.41  4720.6 1204.81  4805.7 1203.00  4842.8 1200.87
  4873.9 1201.67  4930.7 1199.01  4961.8 1199.51  4983.7 1196.64  4984.0 1196.14
  4987.7 1196.64  5014.0 1199.33  5194.3 1205.14  5247.8 1207.64  5434.6 1209.97
  5488.3 1210.23  5502.5 1211.48  5580.2 1212.86  5594.4 1215.27  5643.7 1218.22
  5660.6 1220.65  5686.3 1225.15  5700.4 1229.16  5728.8 1231.46  5750.1 1231.66
#Mann=12,-1,0
  3947.7    0.12       0  3970.0    0.05       0  4053.6    0.12       0
  4159.8    0.05       0  4415.7    0.12       0  4720.6    0.05       0
  4983.7    0.03       0  4987.7    0.05       0  5014.0    0.12       0
  5194.3    0.05       0  5434.6    0.12       0  5660.6    0.05       0
Bank Sta=4983.7,4987.7
Exp/Cntr=0.3,0.1

Type RM Length L Ch R = 1,5000,500,500,500
BEGIN DESCRIPTION:
SANFERNANDO045 10.0
END DESCRIPTION:
XS GIS Cut Line= 3
      2791955.72     10269853.08      2792650.42     10269206.27
      2792755.67     10268703.16
#Sta/Elev= 30
  4050.8 1214.89  4192.2 1212.78  4242.0 1213.22  4255.7 1211.38  4263.0 1211.77
  4439.9 1208.93  4524.9 1206.45  4633.1 1205.47  4638.3 1205.82  4645.1 1205.02
  4801.0 1200.92  4942.2 1196.16  4999.6 1195.49  5004.8 1194.24  5011.4 1193.77
  5011.7 1193.27  5015.4 1193.77  5049.7 1196.65  5105.4 1199.27  5125.8 1199.24
  5194.4 1201.93  5199.5 1202.68  5217.8 1202.60  5344.3 1208.01  5389.2 1210.78
  5422.1 1214.53  5444.2 1215.01  5452.8 1216.90  5483.4 1217.30  5514.0 1219.42
#Mann=5,-1,0
  4050.8    0.12       0  4633.1    0.05       0  4999.6    0.12       0
  5011.4    0.07       0  5015.4    0.12       0
Bank Sta=5011.4,5015.4
Exp/Cntr=0.3,0.1

Type RM Length L Ch R = 1,4500,500,500,500
BEGIN DESCRIPTION:
SANFERNANDO045 9.0
END DESCRIPTION:
XS GIS Cut Line= 3
      2792055.69     10271303.09      2793027.24     10269384.00
      2792755.70     10268553.15
#Sta/Elev= 30
  2849.0 1232.30  2906.5 1229.54  3113.8 1221.51  3122.0 1221.17  3213.8 1219.18
  3337.5 1219.50  3692.6 1214.89  3882.1 1209.59  4137.9 1208.15  4307.3 1205.11
  4500.3 1205.10  4597.5 1203.14  4776.8 1196.82  4978.6 1192.45  4988.4 1189.86
  4988.7 1189.36  4992.4 1189.86  5018.9 1192.32  5060.0 1192.94  5178.3 1196.61
  5242.0 1201.48  5380.1 1206.20  5548.0 1215.23  5621.7 1214.51  5667.0 1219.39
  5693.6 1224.33  5698.8 1222.52  5733.3 1222.62  5800.5 1234.00  5874.1 1231.26
#Mann=11,-1,0
  2849.0    0.05       0  2906.5    0.12       0  3113.8    0.05       0
  3122.0    0.12       0  3337.5    0.05       0  3692.6    0.12       0
  4307.3    0.05       0  4988.4    0.05       0  4992.4    0.05       0
  5060.0    0.12       0  5733.3    0.05       0
Bank Sta=4988.4,4992.4
Exp/Cntr=0.3,0.1

Type RM Length L Ch R = 1,4000,500,500,500
BEGIN DESCRIPTION:
SANFERNANDO045 8.0
END DESCRIPTION:
XS GIS Cut Line= 3
      2792555.66     10270703.15      2793501.08     10269256.00
      2793155.67     10268753.09
#Sta/Elev= 30
  3271.4 1216.49  3637.4 1206.91  3718.0 1206.10  3776.7 1204.76  3911.5 1204.38
  3979.8 1204.81  4108.5 1204.38  4217.1 1201.12  4274.8 1201.90  4436.4 1200.13
  4616.5 1195.35  4853.6 1191.80  4878.6 1190.30  4894.8 1189.54  4955.7 1189.18
  4968.1 1187.33  4977.3 1189.21  4991.5 1189.13  5012.0 1187.08  5012.2 1186.58
  5016.0 1187.08  5027.8 1188.73  5055.9 1189.10  5127.6 1193.03  5149.1 1192.53
  5257.5 1196.30  5366.5 1199.02  5498.8 1206.46  5530.9 1207.20  5610.1 1212.12
#Mann=13,-1,0
  3271.4    0.05       0  3637.4    0.12       0  3718.0    0.05       0
  3911.5    0.12       0  3979.8    0.05       0  4436.4    0.12       0
  4616.5    0.05       0  4878.6    0.12       0  4894.8    0.05       0
  5012.0    0.05       0  5016.0    0.05       0  5257.5    0.12       0
  5498.8    0.05       0
Bank Sta=5012,5016
Exp/Cntr=0.3,0.1

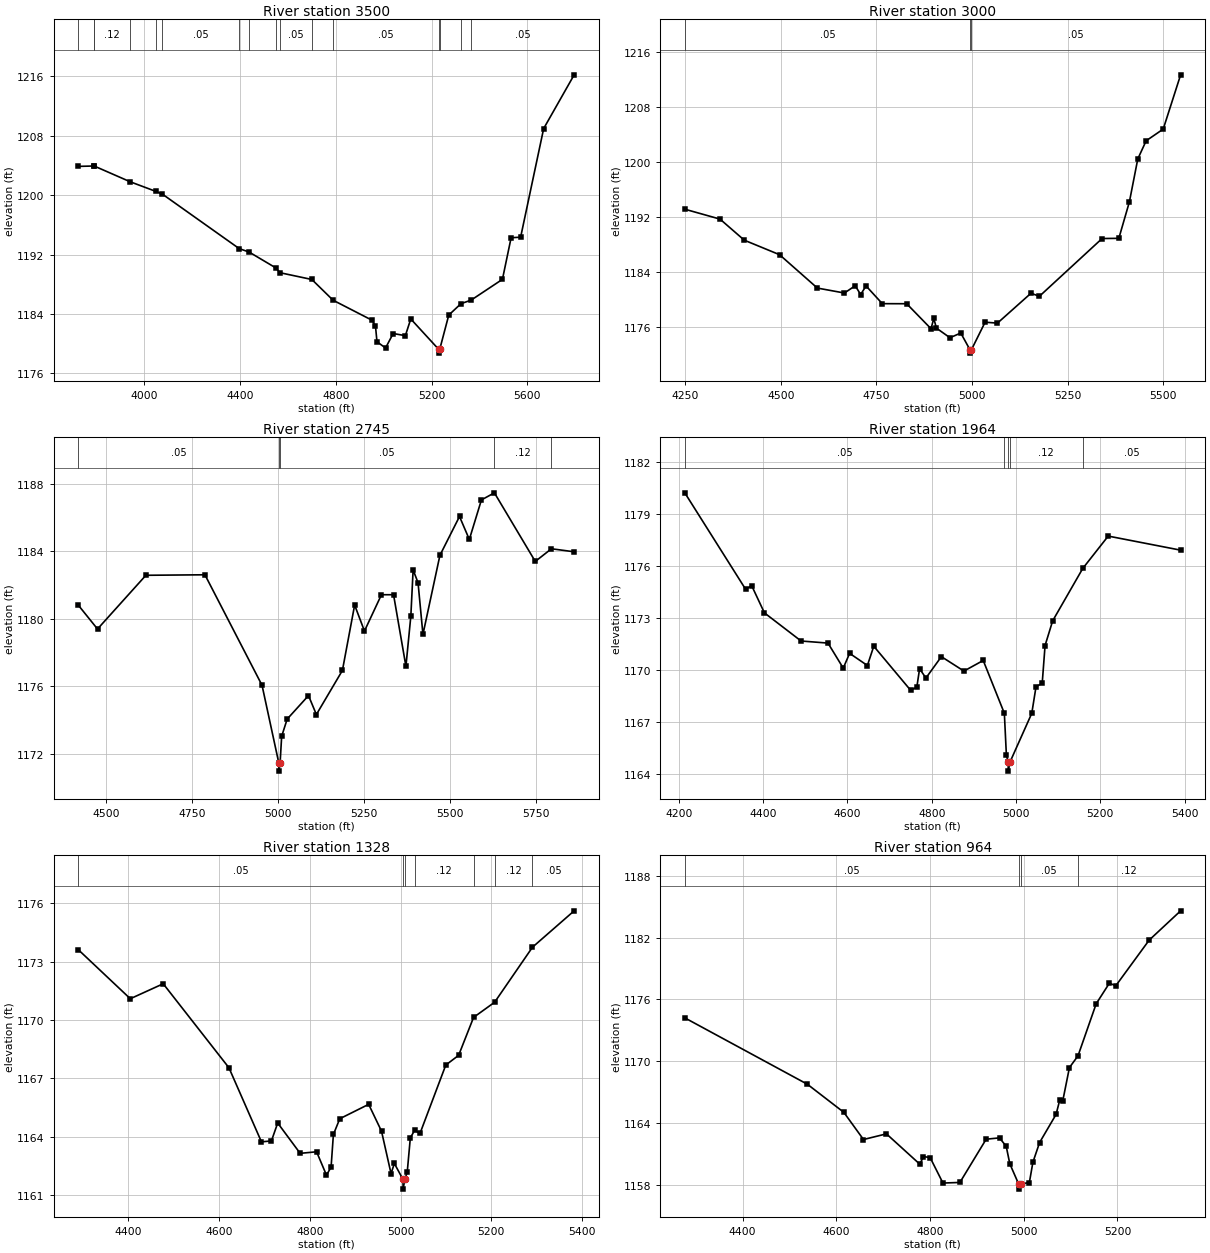
Type RM Length L Ch R = 1,3500,500,500,500
BEGIN DESCRIPTION:
SANFERNANDO045 7.0
END DESCRIPTION:
XS GIS Cut Line= 3
      2792955.72     10270153.08      2793961.75     10269370.12
      2794305.67     10268653.14
#Sta/Elev= 30
  3725.2 1203.86  3789.8 1203.91  3790.6 1203.92  3942.3 1201.78  4049.1 1200.49
  4076.4 1200.12  4397.0 1192.79  4437.7 1192.34  4548.6 1190.22  4567.2 1189.55
  4700.1 1188.64  4788.7 1185.85  4951.2 1183.16  4965.7 1182.39  4972.0 1180.26
  5007.8 1179.42  5039.6 1181.37  5090.5 1181.08  5113.1 1183.33  5229.9 1179.23
  5230.2 1178.73  5233.9 1179.23  5271.7 1183.85  5322.5 1185.38  5365.4 1185.87
  5495.8 1188.66  5532.0 1194.26  5571.7 1194.33  5667.9 1208.95  5795.2 1216.18
#Mann=16,-1,0
  3725.2    0.12       0  3789.8    0.05       0  3790.6    0.12       0
  3942.3    0.05       0  4049.1    0.12       0  4076.4    0.05       0
  4397.0    0.12       0  4437.7    0.05       0  4548.6    0.12       0
  4567.2    0.05       0  4700.1    0.12       0  4788.7    0.05       0
  5229.9    0.03       0  5233.9    0.05       0  5322.5    0.12       0
  5365.4    0.05       0
Bank Sta=5229.9,5233.9
Exp/Cntr=0.3,0.1

Type RM Length L Ch R = 1,3000,255,255,255
BEGIN DESCRIPTION:
SANFERNANDO045 6.0
END DESCRIPTION:
XS GIS Cut Line= 3
      2793855.69     10269903.11      2794397.38     10269383.09
      2794655.70     10268903.08
#Sta/Elev= 30
  4249.1 1193.16  4341.1 1191.72  4404.6 1188.65  4496.7 1186.54  4595.6 1181.68
  4666.3 1180.96  4694.6 1182.02  4708.7 1180.74  4722.9 1181.99  4765.3 1179.41
  4829.1 1179.40  4892.7 1175.76  4899.9 1177.26  4906.8 1175.85  4942.2 1174.45
  4970.4 1175.14  4994.4 1172.71  4994.6 1172.21  4998.4 1172.71  5034.0 1176.71
  5066.4 1176.58  5154.0 1180.93  5175.9 1180.48  5339.8 1188.89  5383.6 1188.92
  5411.2 1194.23  5433.1 1200.47  5455.0 1203.12  5499.6 1204.82  5545.1 1212.72
#Mann=3,-1,0
  4249.1    0.05       0  4994.4    0.05       0  4998.4    0.05       0
Bank Sta=4994.4,4998.4
Exp/Cntr=0.3,0.1

Type RM Length L Ch R = 1,2745,781,781,781
BEGIN DESCRIPTION:
Mapping XS 6dc1098e
END DESCRIPTION:
XS GIS Cut Line= 3
      2794333.64     10270063.07      2794637.44     10269444.62
      2795199.68     10268947.25
#Sta/Elev= 30
  4420.0 1180.80  4475.7 1179.39  4616.2 1182.57  4787.6 1182.60  4953.4 1176.06
  5001.9 1171.48  5002.2 1170.98  5005.9 1171.48  5010.4 1173.04  5026.4 1174.06
  5088.3 1175.45  5111.2 1174.33  5186.8 1176.94  5222.3 1180.81  5250.8 1179.27
  5300.1 1181.42  5335.3 1181.42  5371.2 1177.18  5385.5 1180.16  5392.1 1182.89
  5406.4 1182.13  5420.6 1179.07  5469.9 1183.75  5526.8 1186.05  5555.3 1184.69
  5590.4 1187.03  5628.1 1187.45  5746.8 1183.39  5793.7 1184.14  5859.7 1183.96
#Mann=5,-1,0
  4420.0    0.05       0  5001.9    0.05       0  5005.9    0.05       0
  5628.1    0.12       0  5793.7    0.05       0
Bank Sta=5001.9,5005.9
Exp/Cntr=0.3,0.1

Type RM Length L Ch R = 1,1964,636,636,636
BEGIN DESCRIPTION:
Mapping XS b1339a67
END DESCRIPTION:
XS GIS Cut Line= 3
      2794876.14     10270204.18      2795201.68     10269705.03
      2795407.84     10269162.50
#Sta/Elev= 30
  4214.2 1180.21  4358.7 1174.65  4372.8 1174.87  4403.1 1173.30  4490.1 1171.68
  4553.9 1171.56  4590.1 1170.12  4605.2 1170.97  4647.4 1170.27  4662.5 1171.38
  4750.1 1168.84  4764.7 1169.03  4771.2 1170.08  4786.3 1169.55  4822.9 1170.78
  4876.4 1169.95  4922.2 1170.56  4972.3 1167.52  4977.1 1165.13  4981.3 1164.69
  4981.6 1164.19  4985.3 1164.69  5037.4 1167.52  5047.5 1169.06  5062.1 1169.24
  5068.9 1171.42  5086.9 1172.84  5158.4 1175.86  5218.7 1177.72  5390.5 1176.91
#Mann=5,-1,0
  4214.2    0.05       0  4972.3    0.12       0  4981.3    0.07       0
  4985.3    0.12       0  5158.4    0.05       0
Bank Sta=4981.3,4985.3
Exp/Cntr=0.3,0.1

Type RM Length L Ch R = 1,1328,364,364,364
BEGIN DESCRIPTION:
Mapping XS bc8f6737
END DESCRIPTION:
XS GIS Cut Line= 3
      2795277.61     10270182.48      2795744.21     10269878.64
      2796111.90     10269489.33
#Sta/Elev= 30
  4290.2 1173.62  4404.7 1171.10  4477.2 1171.87  4622.0 1167.55  4693.6 1163.74
  4715.6 1163.79  4729.4 1164.71  4778.9 1163.15  4815.1 1163.23  4836.8 1162.03
  4847.0 1162.44  4852.1 1164.12  4866.2 1164.93  4929.8 1165.67  4958.1 1164.29
  4979.1 1162.11  4986.4 1162.63  5005.4 1161.81  5005.7 1161.31  5009.4 1161.81
  5014.7 1162.17  5021.6 1163.95  5031.0 1164.33  5043.0 1164.18  5099.7 1167.69
  5128.0 1168.19  5160.9 1170.14  5207.3 1170.92  5290.7 1173.75  5382.5 1175.62
#Mann=7,-1,0
  4290.2    0.05       0  5005.4    0.05       0  5009.4    0.05       0
  5031.0    0.12       0  5160.9    0.05       0  5207.3    0.12       0
  5290.7    0.05       0
Bank Sta=5005.4,5009.4
Exp/Cntr=0.3,0.1

Type RM Length L Ch R = 1,964,642,642,642
BEGIN DESCRIPTION:
Mapping XS e85b94f0
END DESCRIPTION:
XS GIS Cut Line= 3
      2795451.25     10270345.22      2795874.42     10270215.02
      2796340.86     10269813.66
#Sta/Elev= 30
  4276.7 1174.21  4538.3 1167.76  4616.1 1165.03  4658.0 1162.39  4707.0 1162.94
  4778.3 1159.99  4785.9 1160.73  4800.2 1160.64  4827.6 1158.16  4863.8 1158.22
  4919.8 1162.42  4948.3 1162.55  4962.6 1161.73  4970.3 1160.03  4989.1 1158.07
  4989.4 1157.57  4993.1 1158.07  5012.0 1158.21  5019.6 1160.19  5033.9 1162.10
  5069.0 1164.83  5076.7 1166.20  5083.3 1166.15  5097.5 1169.38  5115.8 1170.52
  5154.6 1175.58  5182.9 1177.59  5196.3 1177.32  5267.6 1181.76  5334.8 1184.61
#Mann=4,-1,0
  4276.7    0.05       0  4989.1    0.03       0  4993.1    0.05       0
  5115.8    0.12       0
Bank Sta=4989.1,4993.1
Exp/Cntr=0.3,0.1

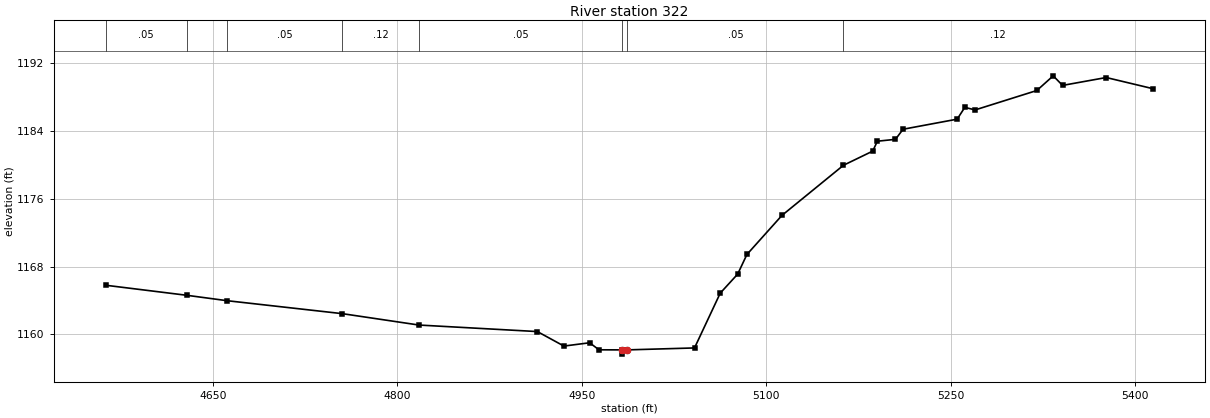
Type RM Length L Ch R = 1,322,0,0,0
BEGIN DESCRIPTION:
SANFERNANDO045 4.0
END DESCRIPTION:
XS GIS Cut Line= 3
      2796071.73     10270885.02      2796484.41     10270422.34
      2796671.21     10270285.40
#Sta/Elev= 30
  4563.0 1165.79  4628.7 1164.61  4661.6 1163.97  4755.4 1162.44  4817.6 1161.10
  4913.9 1160.33  4935.5 1158.62  4956.4 1159.01  4964.0 1158.18  4982.8 1158.17
  4983.0 1157.67  4987.0 1158.17  5041.7 1158.40  5062.6 1164.86  5076.8 1167.11
  5084.3 1169.42  5112.8 1174.03  5162.8 1179.94  5186.6 1181.61  5190.4 1182.78
  5205.1 1183.00  5211.3 1184.19  5255.3 1185.38  5261.5 1186.77  5269.9 1186.47
  5320.1 1188.76  5333.4 1190.49  5341.0 1189.36  5376.5 1190.29  5414.6 1188.97
#Mann=8,-1,0
  4563.0    0.05       0  4628.7    0.12       0  4661.6    0.05       0
  4755.4    0.12       0  4817.6    0.05       0  4982.8    0.03       0
  4987.0    0.05       0  5162.8    0.12       0
Bank Sta=4982.8,4987
Exp/Cntr=0.3,0.1

Chan Stop Cuts=-1