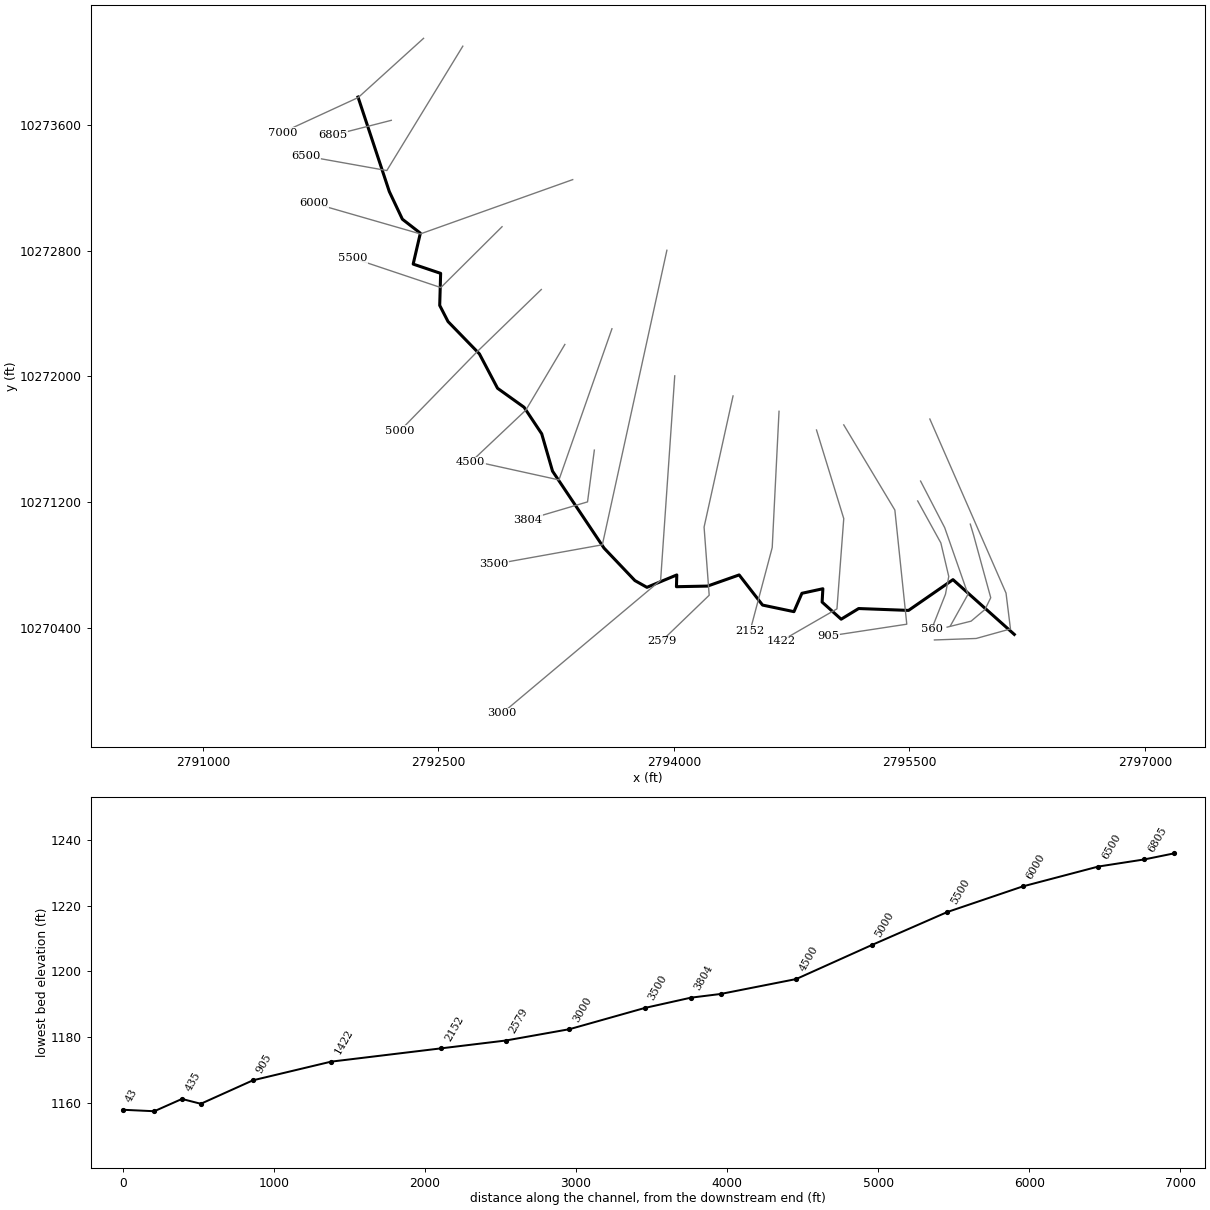
--- SANFERNANDO046.prj (project) ---

Proj Title=SANFERNANDO046 Base Level Engineering
Current Plan=p01
Default Exp/Contr=0.3,0.1
English Units
Geom File=g01
Flow File=f01
Plan File=p01
BEGIN DESCRIPTION:
SANFERNANDO046
END DESCRIPTION:

--- SANFERNANDO046.p01 (plan) ---

Plan Title=Multiple Run
Short Identifier=Multiple
Geom File=g01
Flow File=f01
Subcritical Flow
K Sum by GR= 0
Std Step Tol= 0.01
Critical Tol= 0.01
Num of Std Step Trials= 20
Max Error Tol= 0.3
Flow Tol Ratio= 0.001
Split Flow NTrial= 30
Split Flow Tol= 0.02
Split Flow Ratio= 0.02
Log Output Level= 0
Friction Slope Method= 1
Unsteady Friction Slope Method= 2
Unsteady Bridges Friction Slope Method= 1
Parabolic Critical Depth
Global Vel Dist=  1 , 1 , 1
Global Log Level= 0
CheckData=True
Encroach Param= -1, 0, 0, 0
BEGIN DESCRIPTION:
Multiple Run
END DESCRIPTION:

--- SANFERNANDO046.f01 (steady flow) ---

Flow Title=Multiple
Number of Profiles=7
Profile Names=10-year,25-year,50-year,1pct_min,100-year,1pct_plu,500-year
River Rch & RM= SANFERNANDO046,Reach-1,7000
     305     484     605     402     795    1571    1098
Boundary for River Rch & Prof#=SANFERNANDO046,Reach-1,1
Up Type=0
Dn Type=3
Dn Slope=0.005
Boundary for River Rch & Prof#=SANFERNANDO046,Reach-1,2
Up Type=0
Dn Type=3
Dn Slope=0.005
Boundary for River Rch & Prof#=SANFERNANDO046,Reach-1,3
Up Type=0
Dn Type=3
Dn Slope=0.005
Boundary for River Rch & Prof#=SANFERNANDO046,Reach-1,4
Up Type=0
Dn Type=3
Dn Slope=0.005
Boundary for River Rch & Prof#=SANFERNANDO046,Reach-1,5
Up Type=0
Dn Type=3
Dn Slope=0.005
Boundary for River Rch & Prof#=SANFERNANDO046,Reach-1,6
Up Type=0
Dn Type=3
Dn Slope=0.005
Boundary for River Rch & Prof#=SANFERNANDO046,Reach-1,7
Up Type=0
Dn Type=3
Dn Slope=0.005

--- SANFERNANDO046.g01 (geometry) ---

Geom Title=Existing Conditions

River Reach=SANFERNANDO046,Reach-1
Reach XY= 30
      2791988.25     10273779.00      2792187.50     10273177.00
      2792270.75     10273001.00      2792385.25     10272912.00
      2792339.50     10272715.00      2792514.50     10272656.00
      2792508.50     10272452.00      2792561.50     10272349.00
      2792761.50     10272143.00      2792877.00     10271924.00
      2793046.00     10271803.00      2793158.25     10271634.00
      2793227.25     10271396.00      2793555.25     10270906.00
      2793752.00     10270699.00      2793828.50     10270656.00
      2794018.75     10270735.00      2794016.50     10270660.00
      2794214.75     10270664.00      2794416.00     10270735.00
      2794565.00     10270543.00      2794765.00     10270501.00
      2794815.75     10270618.00      2794949.25     10270647.00
      2794944.50     10270562.00      2795065.75     10270453.00
      2795177.25     10270521.00      2795495.00     10270509.00
      2795778.00     10270705.00      2796168.75     10270356.00

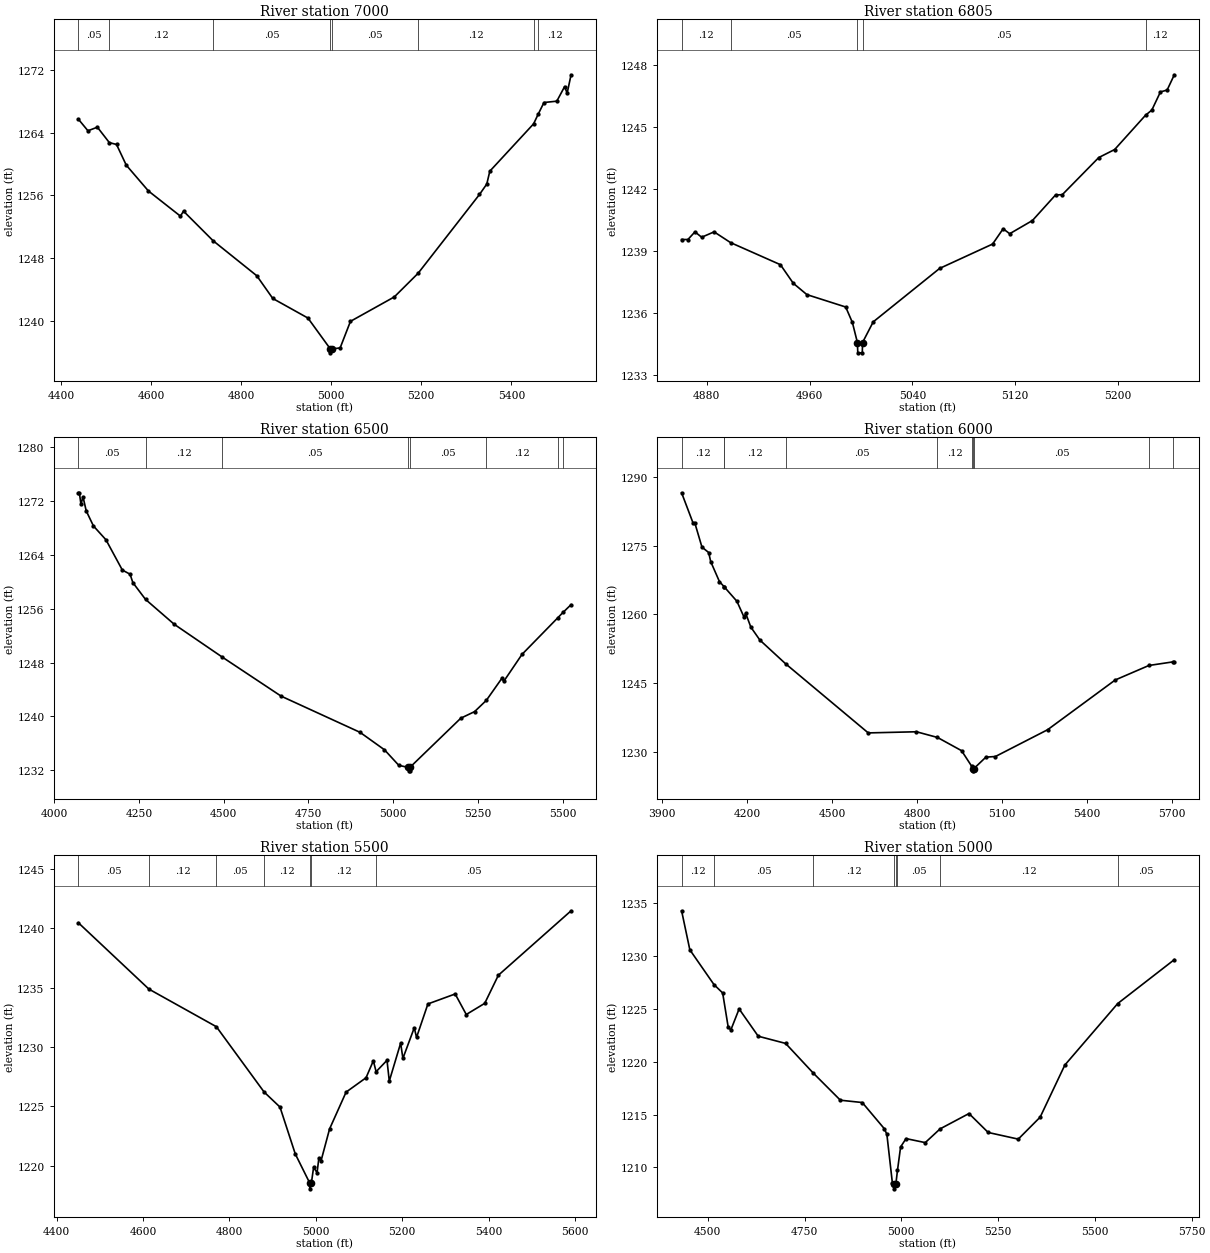
Type RM Length L Ch R = 1,7000,195,195,195
BEGIN DESCRIPTION:
SANFERNANDO046 14.0
END DESCRIPTION:
XS GIS Cut Line= 3
      2792405.66     10274153.09      2791989.46     10273776.03
      2791505.65     10273553.10
#Sta/Elev= 30
  4438.4 1265.73  4459.7 1264.25  4480.6 1264.71  4507.2 1262.74  4523.2 1262.50
  4544.8 1259.86  4594.1 1256.56  4665.1 1253.35  4671.9 1253.99  4737.5 1250.22
  4834.7 1245.74  4870.2 1242.84  4948.3 1240.34  4998.0 1236.40  4998.2 1235.90
  5002.0 1236.40  5019.8 1236.53  5042.7 1239.92  5140.1 1243.04  5193.0 1246.06
  5329.3 1256.12  5345.5 1257.45  5352.2 1259.09  5449.5 1265.14  5459.4 1266.34
  5472.5 1267.86  5501.0 1268.03  5518.4 1269.90  5523.9 1269.04  5532.7 1271.40
#Mann=8,-1,0
  4438.4    0.05       0  4507.2    0.12       0  4737.5    0.05       0
  4998.0    0.05       0  5002.0    0.05       0  5193.0    0.12       0
  5449.5    0.05       0  5459.4    0.12       0
Bank Sta=4998,5002
Exp/Cntr=0.3,0.1

Type RM Length L Ch R = 1,6805,305,305,305
BEGIN DESCRIPTION:
Mapping XS 2af3cd12
END DESCRIPTION:
XS GIS Cut Line= 2
      2792200.18     10273630.85      2791828.74     10273535.83
#Sta/Elev= 30
  4860.4 1239.56  4865.3 1239.56  4870.8 1239.93  4876.0 1239.67  4885.7 1239.93
  4898.5 1239.41  4937.3 1238.34  4947.3 1237.44  4957.9 1236.89  4988.1 1236.29
  4993.3 1235.54  4997.2 1234.57  4997.5 1234.07  5001.0 1234.07  5001.2 1234.57
  5009.5 1235.57  5061.2 1238.16  5102.4 1239.34  5110.6 1240.08  5115.7 1239.84
  5133.4 1240.48  5151.4 1241.72  5156.6 1241.73  5185.0 1243.53  5197.4 1243.92
  5221.4 1245.58  5226.3 1245.83  5233.0 1246.71  5238.2 1246.80  5243.8 1247.54
#Mann=5,-1,0
  4860.4    0.12       0  4898.5    0.05       0  4997.2    0.03       0
  5001.2    0.05       0  5221.4    0.12       0
Bank Sta=4997.2,5001.2
Exp/Cntr=0.3,0.1

Type RM Length L Ch R = 1,6500,500,500,500
BEGIN DESCRIPTION:
SANFERNANDO046 13.0
END DESCRIPTION:
XS GIS Cut Line= 3
      2792655.69     10274103.12      2792171.62     10273310.91
      2791655.70     10273403.11
#Sta/Elev= 30
  4071.6 1273.26  4074.5 1273.26  4079.3 1271.52  4085.2 1272.67  4094.8 1270.56
  4116.1 1268.32  4152.9 1266.27  4201.3 1261.76  4224.0 1261.15  4232.2 1259.90
  4269.6 1257.40  4354.2 1253.70  4494.3 1248.87  4669.3 1243.01  4901.9 1237.63
  4974.0 1235.03  5016.2 1232.72  5044.7 1232.40  5044.9 1231.90  5048.4 1231.90
  5048.7 1232.40  5199.0 1239.73  5239.7 1240.71  5274.4 1242.39  5320.5 1245.69
  5325.6 1245.21  5379.4 1249.22  5485.4 1254.69  5500.4 1255.47  5524.1 1256.62
#Mann=8,-1,0
  4071.6    0.05       0  4269.6    0.12       0  4494.3    0.05       0
  5044.7    0.03       0  5048.7    0.05       0  5274.4    0.12       0
  5485.4    0.05       0  5500.4    0.12       0
Bank Sta=5044.7,5048.7
Exp/Cntr=0.3,0.1

Type RM Length L Ch R = 1,6000,500,500,500
BEGIN DESCRIPTION:
SANFERNANDO046 12.0
END DESCRIPTION:
XS GIS Cut Line= 3
      2793355.71     10273253.12      2792385.31     10272907.25
      2791705.67     10273103.12
#Sta/Elev= 30
  3969.8 1286.55  4010.7 1279.87  4016.1 1280.03  4041.6 1274.69  4065.4 1273.50
  4072.4 1271.53  4103.2 1267.17  4120.7 1265.98  4120.9 1265.96  4164.8 1262.87
  4190.3 1259.36  4195.6 1260.27  4214.0 1257.22  4245.8 1254.40  4336.4 1249.23
  4628.0 1234.13  4797.9 1234.38  4872.1 1233.14  4957.1 1230.25  4993.2 1226.81
  4996.7 1226.35  4997.0 1225.85  5000.7 1226.35  5042.8 1228.84  5076.5 1228.98
  5260.4 1234.82  5499.1 1245.69  5617.7 1248.85  5704.1 1249.65  5707.3 1249.65
#Mann=10,-1,0
  3969.8    0.12       0  4120.7    0.05       0  4120.9    0.12       0
  4336.4    0.05       0  4872.1    0.12       0  4993.2    0.05       0
  4996.7    0.05       0  5000.7    0.05       0  5617.7    0.12       0
  5704.1    0.05       0
Bank Sta=4996.7,5000.7
Exp/Cntr=0.3,0.1

Type RM Length L Ch R = 1,5500,500,500,500
BEGIN DESCRIPTION:
SANFERNANDO046 11.0
END DESCRIPTION:
XS GIS Cut Line= 3
      2792905.70     10272953.13      2792515.79     10272565.52
      2791955.67     10272753.12
#Sta/Elev= 30
  4450.2 1240.46  4613.5 1234.87  4769.7 1231.70  4880.1 1226.20  4916.9 1224.93
  4952.3 1220.98  4985.6 1218.54  4985.9 1218.04  4989.6 1218.54  4994.7 1219.85
  5002.7 1219.40  5006.8 1220.60  5012.0 1220.41  5031.7 1223.09  5069.9 1226.19
  5116.1 1227.40  5133.0 1228.83  5139.4 1227.91  5164.6 1228.87  5169.9 1227.12
  5196.2 1230.32  5201.4 1229.03  5227.7 1231.61  5233.0 1230.80  5259.3 1233.62
  5322.4 1234.46  5348.1 1232.73  5390.8 1233.67  5422.4 1236.04  5590.7 1241.47
#Mann=7,-1,0
  4450.2    0.05       0  4613.5    0.12       0  4769.7    0.05       0
  4880.1    0.12       0  4985.6    0.07       0  4989.6    0.12       0
  5139.4    0.05       0
Bank Sta=4985.6,4989.6
Exp/Cntr=0.3,0.1

Type RM Length L Ch R = 1,5000,500,500,500
BEGIN DESCRIPTION:
SANFERNANDO046 10.0
END DESCRIPTION:
XS GIS Cut Line= 3
      2793155.71     10272553.13      2792747.97     10272157.98
      2792255.65     10271653.08
#Sta/Elev= 30
  4432.2 1234.27  4453.5 1230.58  4515.9 1227.29  4538.3 1226.50  4552.5 1223.29
  4559.4 1223.00  4580.8 1224.99  4630.2 1222.41  4700.9 1221.73  4772.5 1218.92
  4842.4 1216.36  4899.0 1216.14  4955.6 1213.68  4962.5 1213.15  4976.7 1208.56
  4981.9 1208.48  4982.1 1207.98  4985.9 1208.48  4990.0 1209.74  4998.0 1211.94
  5012.1 1212.73  5061.7 1212.35  5100.1 1213.65  5174.7 1215.10  5224.3 1213.31
  5302.0 1212.68  5358.6 1214.76  5422.3 1219.68  5559.0 1225.50  5705.2 1229.65
#Mann=8,-1,0
  4432.2    0.12       0  4515.9    0.05       0  4772.5    0.12       0
  4981.9    0.05       0  4985.9    0.12       0  4990.0    0.05       0
  5100.1    0.12       0  5559.0    0.05       0
Bank Sta=4981.9,4985.9
Exp/Cntr=0.3,0.1

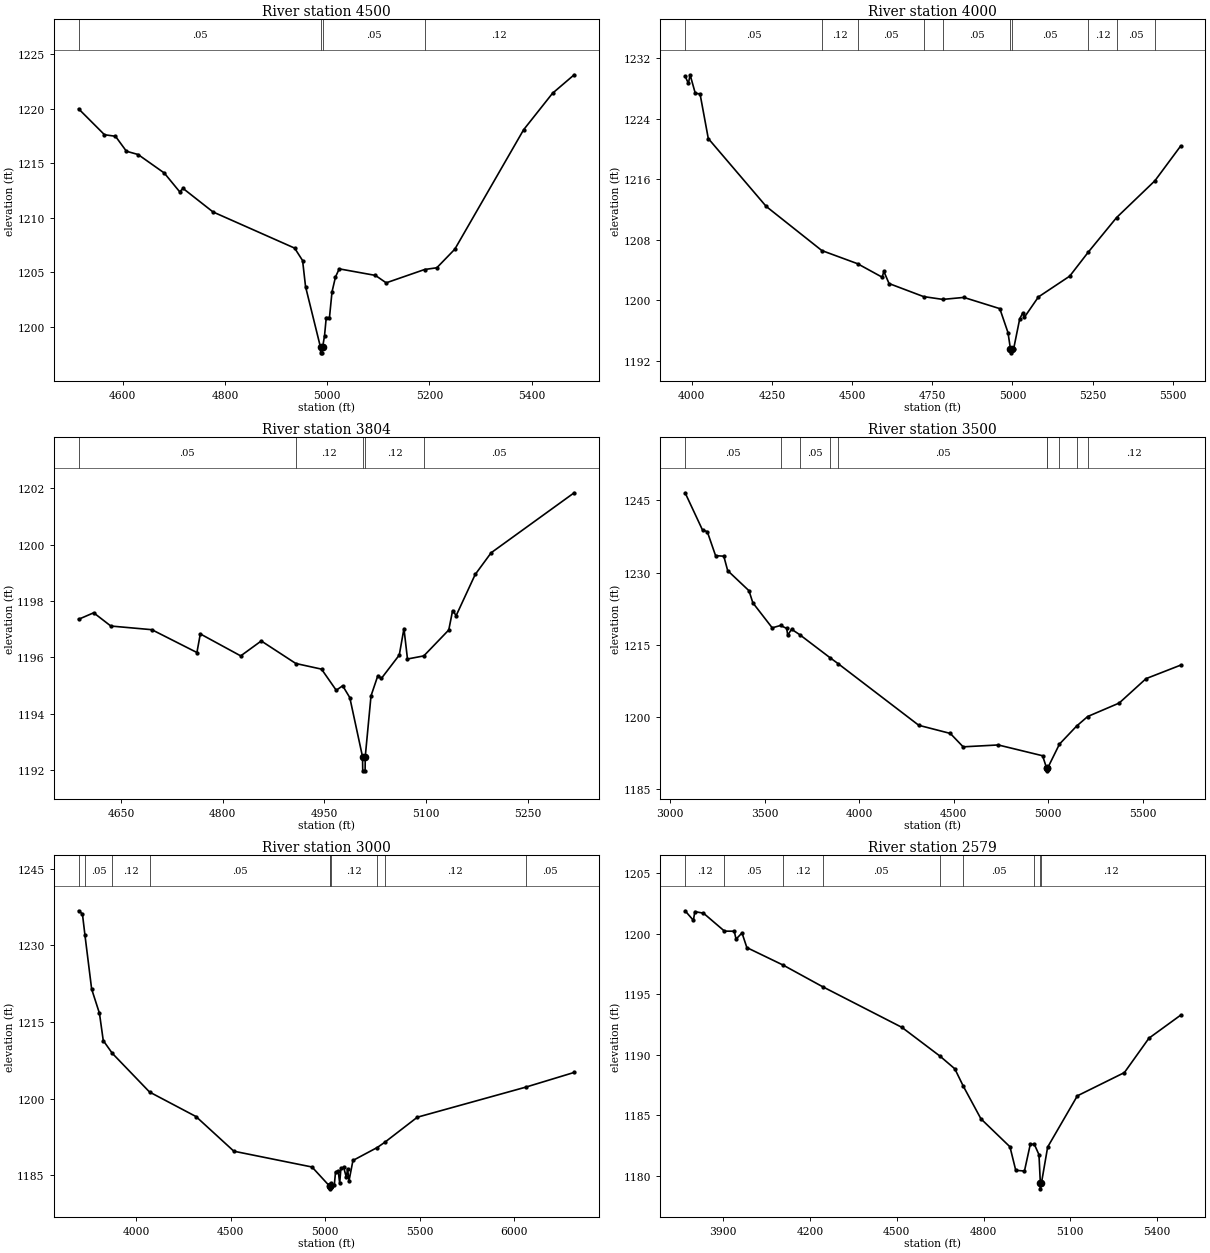
Type RM Length L Ch R = 1,4500,500,500,500
BEGIN DESCRIPTION:
SANFERNANDO046 9.0
END DESCRIPTION:
XS GIS Cut Line= 3
      2793305.68     10272203.10      2793057.22     10271784.95
      2792705.70     10271453.12
#Sta/Elev= 30
  4513.6 1219.97  4564.2 1217.60  4585.7 1217.46  4607.1 1216.09  4629.9 1215.79
  4681.1 1214.10  4711.3 1212.38  4718.1 1212.68  4776.6 1210.53  4936.3 1207.22
  4951.9 1206.08  4957.7 1203.69  4987.0 1198.13  4987.2 1197.63  4990.7 1197.63
  4991.0 1198.13  4994.8 1199.18  4998.2 1200.86  5004.5 1200.86  5009.5 1203.22
  5016.3 1204.58  5023.6 1205.32  5094.4 1204.72  5115.5 1204.04  5190.7 1205.26
  5214.6 1205.42  5249.8 1207.12  5384.5 1218.06  5441.1 1221.40  5483.4 1223.09
#Mann=4,-1,0
  4513.6    0.05       0  4987.0    0.05       0  4991.0    0.05       0
  5190.7    0.12       0
Bank Sta=4987,4991
Exp/Cntr=0.3,0.1

Type RM Length L Ch R = 1,4000,196,196,196
BEGIN DESCRIPTION:
SANFERNANDO046 8.0
END DESCRIPTION:
XS GIS Cut Line= 3
      2793605.70     10272303.16      2793268.01     10271340.26
      2792755.69     10271453.11
#Sta/Elev= 30
  3979.6 1229.59  3989.9 1228.63  3995.2 1229.77  4011.4 1227.32  4026.2 1227.25
  4051.9 1221.36  4232.6 1212.40  4406.0 1206.58  4517.2 1204.85  4594.0 1203.07
  4599.3 1203.83  4615.5 1202.23  4723.1 1200.51  4782.9 1200.14  4848.6 1200.40
  4960.8 1198.92  4986.4 1195.75  4994.0 1193.59  4994.2 1193.09  4998.0 1193.59
  5003.8 1193.59  5022.9 1197.58  5032.2 1198.33  5037.4 1197.78  5081.1 1200.46
  5178.8 1203.21  5236.7 1206.38  5325.0 1210.94  5444.4 1215.79  5524.6 1220.37
#Mann=10,-1,0
  3979.6    0.05       0  4406.0    0.12       0  4517.2    0.05       0
  4723.1    0.12       0  4782.9    0.05       0  4994.0    0.05       0
  4998.0    0.05       0  5236.7    0.12       0  5325.0    0.05       0
  5444.4    0.12       0
Bank Sta=4994,4998
Exp/Cntr=0.3,0.1

Type RM Length L Ch R = 1,3804,304,304,304
BEGIN DESCRIPTION:
Mapping XS fb11e3af
END DESCRIPTION:
XS GIS Cut Line= 3
      2793493.56     10271530.19      2793450.16     10271200.29
      2793068.22     10271087.44
#Sta/Elev= 30
  4587.6 1197.35  4609.8 1197.58  4635.1 1197.11  4695.6 1196.98  4762.1 1196.17
  4767.1 1196.83  4826.7 1196.05  4857.0 1196.58  4908.0 1195.78  4945.9 1195.58
  4967.6 1194.83  4977.1 1194.99  4987.6 1194.57  5006.4 1192.47  5006.7 1191.97
  5010.2 1191.97  5010.4 1192.47  5018.9 1194.63  5029.0 1195.35  5034.2 1195.25
  5060.6 1196.08  5067.5 1197.02  5072.7 1195.94  5096.8 1196.05  5133.6 1196.97
  5139.3 1197.66  5144.5 1197.48  5172.6 1198.94  5196.1 1199.71  5318.6 1201.84
#Mann=5,-1,0
  4587.6    0.05       0  4908.0    0.12       0  5006.4    0.07       0
  5010.4    0.12       0  5096.8    0.05       0
Bank Sta=5006.4,5010.4
Exp/Cntr=0.3,0.1

Type RM Length L Ch R = 1,3500,500,500,500
BEGIN DESCRIPTION:
SANFERNANDO046 7.0
END DESCRIPTION:
XS GIS Cut Line= 3
      2793955.68     10272803.11      2793544.60     10270927.02
      2792855.65     10270803.11
#Sta/Elev= 30
  3079.4 1246.54  3171.5 1238.81  3196.7 1238.48  3240.5 1233.50  3284.1 1233.38
  3304.6 1230.39  3417.2 1226.22  3437.7 1223.71  3540.1 1218.52  3584.0 1219.01
  3616.8 1218.40  3622.0 1216.98  3642.5 1218.23  3685.5 1217.10  3846.9 1212.29
  3888.6 1211.09  4315.2 1198.30  4481.9 1196.61  4549.8 1193.83  4735.3 1194.22
  4969.9 1191.98  4991.8 1189.35  4992.0 1188.85  4995.8 1189.35  5059.1 1194.39
  5149.9 1198.14  5208.4 1200.12  5374.8 1202.91  5517.1 1207.98  5700.0 1210.78
#Mann=10,-1,0
  3079.4    0.05       0  3584.0    0.12       0  3685.5    0.05       0
  3846.9    0.12       0  3888.6    0.05       0  4991.8    0.03       0
  4995.8    0.05       0  5059.1    0.12       0  5149.9    0.05       0
  5208.4    0.12       0
Bank Sta=4991.8,4995.8
Exp/Cntr=0.3,0.1

Type RM Length L Ch R = 1,3000,421,421,421
BEGIN DESCRIPTION:
SANFERNANDO046 6.0
END DESCRIPTION:
XS GIS Cut Line= 3
      2794005.69     10272003.16      2793915.77     10270701.06
      2792905.70     10269853.12
#Sta/Elev= 30
  3694.8 1236.76  3714.9 1236.15  3728.2 1232.01  3763.7 1221.45  3805.1 1216.70
  3825.2 1211.37  3873.1 1208.88  4070.6 1201.30  4316.3 1196.51  4516.8 1189.73
  4930.7 1186.64  5024.4 1182.87  5024.7 1182.37  5028.4 1182.87  5031.8 1183.44
  5048.5 1183.03  5055.1 1185.66  5069.4 1185.87  5077.1 1183.48  5083.7 1186.37
  5098.0 1186.59  5112.3 1184.64  5118.8 1186.32  5126.6 1183.95  5147.4 1187.92
  5275.8 1190.45  5315.4 1191.46  5488.2 1196.38  6061.3 1202.25  6318.8 1205.14
#Mann=10,-1,0
  3694.8    0.12       0  3728.2    0.05       0  3873.1    0.12       0
  4070.6    0.05       0  5024.4    0.03       0  5028.4    0.05       0
  5031.8    0.12       0  5275.8    0.05       0  5315.4    0.12       0
  6061.3    0.05       0
Bank Sta=5024.4,5028.4
Exp/Cntr=0.3,0.1

Type RM Length L Ch R = 1,2579,427,427,427
BEGIN DESCRIPTION:
Mapping XS 89ffc758
END DESCRIPTION:
XS GIS Cut Line= 4
      2794377.03     10271875.21      2794192.56     10271039.67
      2794225.11     10270605.64      2793921.28     10270312.66
#Sta/Elev= 30
  3768.3 1201.88  3796.9 1201.09  3802.0 1201.81  3831.9 1201.68  3904.4 1200.20
  3938.2 1200.19  3944.5 1199.54  3965.0 1200.05  3981.8 1198.84  4107.6 1197.39
  4243.7 1195.61  4518.0 1192.25  4649.3 1189.88  4700.7 1188.83  4729.7 1187.41
  4791.0 1184.70  4891.3 1182.39  4911.3 1180.45  4941.4 1180.39  4961.5 1182.59
  4975.3 1182.61  4991.6 1181.74  4996.3 1179.42  4996.5 1178.92  5000.3 1179.42
  5021.6 1182.37  5124.3 1186.60  5286.9 1188.52  5371.8 1191.36  5481.3 1193.26
#Mann=9,-1,0
  3768.3    0.12       0  3904.4    0.05       0  4107.6    0.12       0
  4243.7    0.05       0  4649.3    0.12       0  4729.7    0.05       0
  4975.3    0.12       0  4996.3    0.07       0  5000.3    0.12       0
Bank Sta=4996.3,5000.3
Exp/Cntr=0.3,0.1

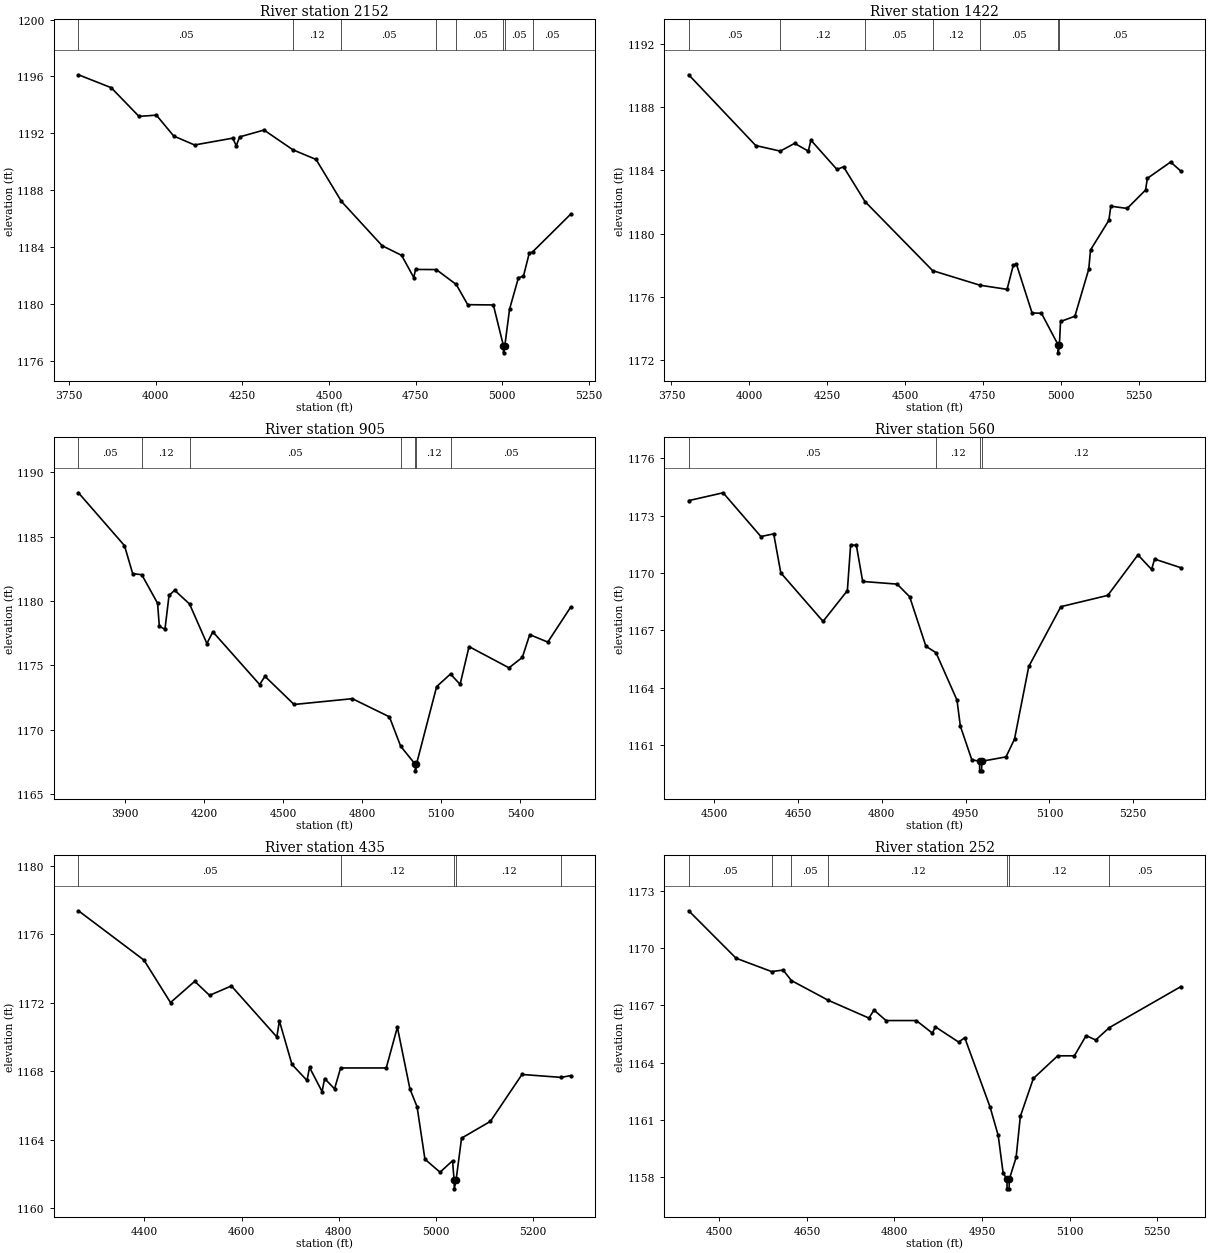
Type RM Length L Ch R = 1,2152,730,730,730
BEGIN DESCRIPTION:
Mapping XS 0d0d2934
END DESCRIPTION:
XS GIS Cut Line= 3
      2794669.99     10271777.50      2794626.59     10270909.46
      2794485.58     10270377.98
#Sta/Elev= 30
  3777.6 1196.11  3872.1 1195.20  3952.2 1193.18  4002.3 1193.27  4052.3 1191.80
  4112.4 1191.17  4222.5 1191.65  4232.6 1191.12  4242.6 1191.74  4312.7 1192.22
  4396.0 1190.83  4462.8 1190.15  4535.9 1187.20  4653.3 1184.08  4709.5 1183.40
  4744.5 1181.84  4749.7 1182.41  4809.4 1182.40  4867.0 1181.35  4900.1 1179.93
  4974.0 1179.91  5003.1 1177.04  5003.3 1176.54  5007.1 1177.04  5020.7 1179.61
  5046.4 1181.83  5060.8 1181.93  5077.5 1183.55  5087.0 1183.64  5196.6 1186.29
#Mann=8,-1,0
  3777.6    0.05       0  4396.0    0.12       0  4535.9    0.05       0
  4809.4    0.12       0  4867.0    0.05       0  5003.1    0.05       0
  5007.1    0.05       0  5087.0    0.05       0
Bank Sta=5003.1,5007.1
Exp/Cntr=0.3,0.1

Type RM Length L Ch R = 1,1422,517,517,517
BEGIN DESCRIPTION:
Mapping XS c8fdba23
END DESCRIPTION:
XS GIS Cut Line= 4
      2794908.70     10271658.20      2795082.32     10271093.92
      2795038.92     10270518.83      2794680.83     10270312.66
#Sta/Elev= 30
  3805.4 1190.04  4020.7 1185.57  4099.4 1185.22  4145.5 1185.71  4189.4 1185.22
  4197.8 1185.91  4281.5 1184.06  4302.5 1184.23  4371.6 1182.03  4588.8 1177.67
  4740.8 1176.75  4827.8 1176.49  4847.9 1178.03  4857.9 1178.07  4908.0 1175.00
  4938.1 1174.98  4991.8 1172.98  4992.0 1172.48  4995.8 1172.98  4999.5 1174.46
  5045.5 1174.79  5090.0 1177.76  5095.8 1178.98  5154.7 1180.85  5160.9 1181.74
  5213.6 1181.60  5272.5 1182.76  5278.3 1183.50  5353.0 1184.53  5385.7 1183.96
#Mann=7,-1,0
  3805.4    0.05       0  4099.4    0.12       0  4371.6    0.05       0
  4588.8    0.12       0  4740.8    0.05       0  4991.8    0.05       0
  4995.8    0.05       0
Bank Sta=4991.8,4995.8
Exp/Cntr=0.3,0.1

Type RM Length L Ch R = 1,905,345,345,345
BEGIN DESCRIPTION:
Mapping XS 30c9345a
END DESCRIPTION:
XS GIS Cut Line= 4
      2795082.34     10271690.67      2795407.84     10271148.18
      2795483.79     10270421.18      2794984.65     10270345.22
#Sta/Elev= 30
  3722.0 1188.42  3896.8 1184.31  3927.9 1182.13  3962.4 1182.05  4022.4 1179.83
  4029.0 1178.05  4050.4 1177.80  4065.9 1180.44  4087.3 1180.84  4143.9 1179.77
  4209.7 1176.70  4232.3 1177.61  4410.0 1173.51  4430.1 1174.15  4540.7 1171.96
  4761.9 1172.41  4902.7 1171.00  4945.6 1168.71  5001.2 1167.30  5001.5 1166.80
  5005.2 1167.30  5082.1 1173.35  5134.7 1174.33  5171.1 1173.52  5205.1 1176.46
  5356.8 1174.81  5407.4 1175.62  5435.5 1177.39  5504.1 1176.81  5590.5 1179.51
#Mann=7,-1,0
  3722.0    0.05       0  3962.4    0.12       0  4143.9    0.05       0
  4945.6    0.12       0  5001.2    0.07       0  5005.2    0.12       0
  5134.7    0.05       0
Bank Sta=5001.2,5005.2
Exp/Cntr=0.3,0.1

Type RM Length L Ch R = 1,560,125,125,125
BEGIN DESCRIPTION:
Mapping XS 07eac1d5
END DESCRIPTION:
XS GIS Cut Line= 5
      2795553.27     10271206.17      2795700.84     10270938.82
      2795751.18     10270725.28      2795730.35     10270612.44
      2795641.83     10270388.52
#Sta/Elev= 30
  4454.7 1173.79  4516.2 1174.20  4583.8 1171.91  4606.7 1172.05  4619.4 1170.01
  4695.0 1167.47  4738.5 1169.08  4744.3 1171.47  4754.6 1171.45  4765.9 1169.56
  4827.6 1169.42  4849.9 1168.76  4879.0 1166.17  4897.1 1165.83  4934.6 1163.35
  4940.6 1161.99  4961.1 1160.23  4974.9 1160.15  4975.2 1159.65  4978.7 1159.65
  4978.9 1160.15  5022.3 1160.38  5037.5 1161.31  5063.0 1165.11  5120.4 1168.24
  5204.3 1168.83  5258.3 1170.95  5282.7 1170.19  5288.1 1170.73  5335.0 1170.28
#Mann=4,-1,0
  4454.7    0.05       0  4897.1    0.12       0  4974.9    0.07       0
  4978.9    0.12       0
Bank Sta=4974.9,4978.9
Exp/Cntr=0.3,0.1

Type RM Length L Ch R = 1,435,183,183,183
BEGIN DESCRIPTION:
Mapping XS 63d3807c
END DESCRIPTION:
XS GIS Cut Line= 4
      2795571.69     10271332.88      2795725.33     10271036.01
      2795873.77     10270611.53      2795761.80     10270411.03
#Sta/Elev= 30
  4264.0 1177.36  4398.9 1174.48  4453.6 1172.00  4503.5 1173.24  4534.0 1172.42
  4579.0 1172.97  4672.6 1169.99  4677.9 1170.93  4703.7 1168.39  4734.7 1167.45
  4740.0 1168.21  4765.8 1166.80  4771.1 1167.56  4791.5 1166.96  4804.0 1168.18
  4898.0 1168.18  4920.9 1170.56  4946.7 1166.96  4961.5 1165.91  4977.7 1162.85
  5008.8 1162.09  5034.5 1162.76  5037.8 1161.62  5038.1 1161.12  5041.8 1161.62
  5053.1 1164.08  5112.5 1165.06  5177.6 1167.80  5257.9 1167.63  5277.6 1167.73
#Mann=5,-1,0
  4264.0    0.05       0  4804.0    0.12       0  5037.8    0.07       0
  5041.8    0.12       0  5257.9    0.05       0
Bank Sta=5037.8,5041.8
Exp/Cntr=0.3,0.1

Type RM Length L Ch R = 1,252,209,209,209
BEGIN DESCRIPTION:
Mapping XS ca67c33d
END DESCRIPTION:
XS GIS Cut Line= 6
      2795888.34     10271058.62      2795909.17     10270989.17
      2796018.55     10270589.87      2795982.09     10270515.21
      2795893.55     10270440.56      2795740.76     10270402.36
#Sta/Elev= 30
  4447.6 1171.97  4528.7 1169.48  4589.6 1168.78  4609.3 1168.86  4623.4 1168.31
  4686.2 1167.28  4756.3 1166.34  4764.9 1166.76  4785.6 1166.21  4837.4 1166.21
  4864.9 1165.55  4870.1 1165.88  4910.0 1165.08  4920.4 1165.31  4963.9 1161.66
  4977.7 1160.18  4986.1 1158.22  4992.7 1157.88  4992.9 1157.38  4996.4 1157.38
  4996.7 1157.88  5008.4 1159.03  5015.6 1161.18  5037.9 1163.17  5079.6 1164.36
  5108.2 1164.36  5128.3 1165.42  5144.7 1165.19  5168.1 1165.84  5290.5 1167.99
#Mann=7,-1,0
  4447.6    0.05       0  4589.6    0.12       0  4623.4    0.05       0
  4686.2    0.12       0  4992.7    0.07       0  4996.7    0.12       0
  5168.1    0.05       0
Bank Sta=4992.7,4996.7
Exp/Cntr=0.3,0.1

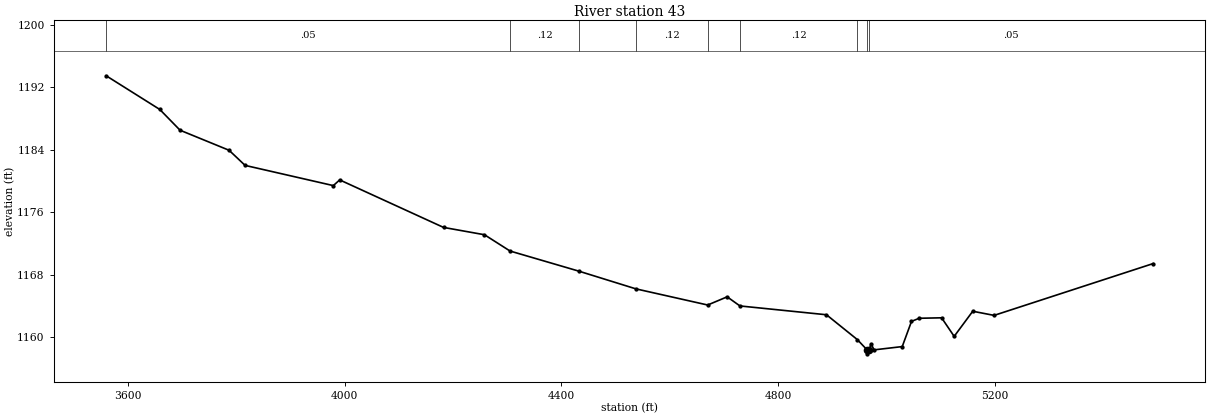
Type RM Length L Ch R = 1,43,0,0,0
BEGIN DESCRIPTION:
SANFERNANDO046 5.0
END DESCRIPTION:
XS GIS Cut Line= 5
      2795630.68     10271728.11      2796115.95     10270619.34
      2796144.25     10270391.00      2795925.85     10270330.28
      2795659.90     10270320.79
#Sta/Elev= 30
  3559.6 1193.48  3658.6 1189.16  3696.0 1186.50  3786.5 1183.93  3816.1 1181.99
  3979.0 1179.40  3990.8 1180.13  4182.5 1174.04  4258.1 1173.10  4305.4 1171.01
  4432.5 1168.43  4537.8 1166.16  4670.3 1164.09  4706.3 1165.14  4729.9 1163.97
  4889.7 1162.84  4946.6 1159.66  4964.8 1158.33  4965.1 1157.83  4968.8 1158.33
  4971.8 1159.12  4977.7 1158.34  5029.6 1158.76  5046.7 1161.99  5060.8 1162.39
  5102.3 1162.45  5125.5 1160.07  5159.8 1163.29  5199.2 1162.76  5492.8 1169.40
#Mann=9,-1,0
  3559.6    0.05       0  4305.4    0.12       0  4432.5    0.05       0
  4537.8    0.12       0  4670.3    0.05       0  4729.9    0.12       0
  4946.6    0.05       0  4964.8    0.03       0  4968.8    0.05       0
Bank Sta=4964.8,4968.8
Exp/Cntr=0.3,0.1

Chan Stop Cuts=-1