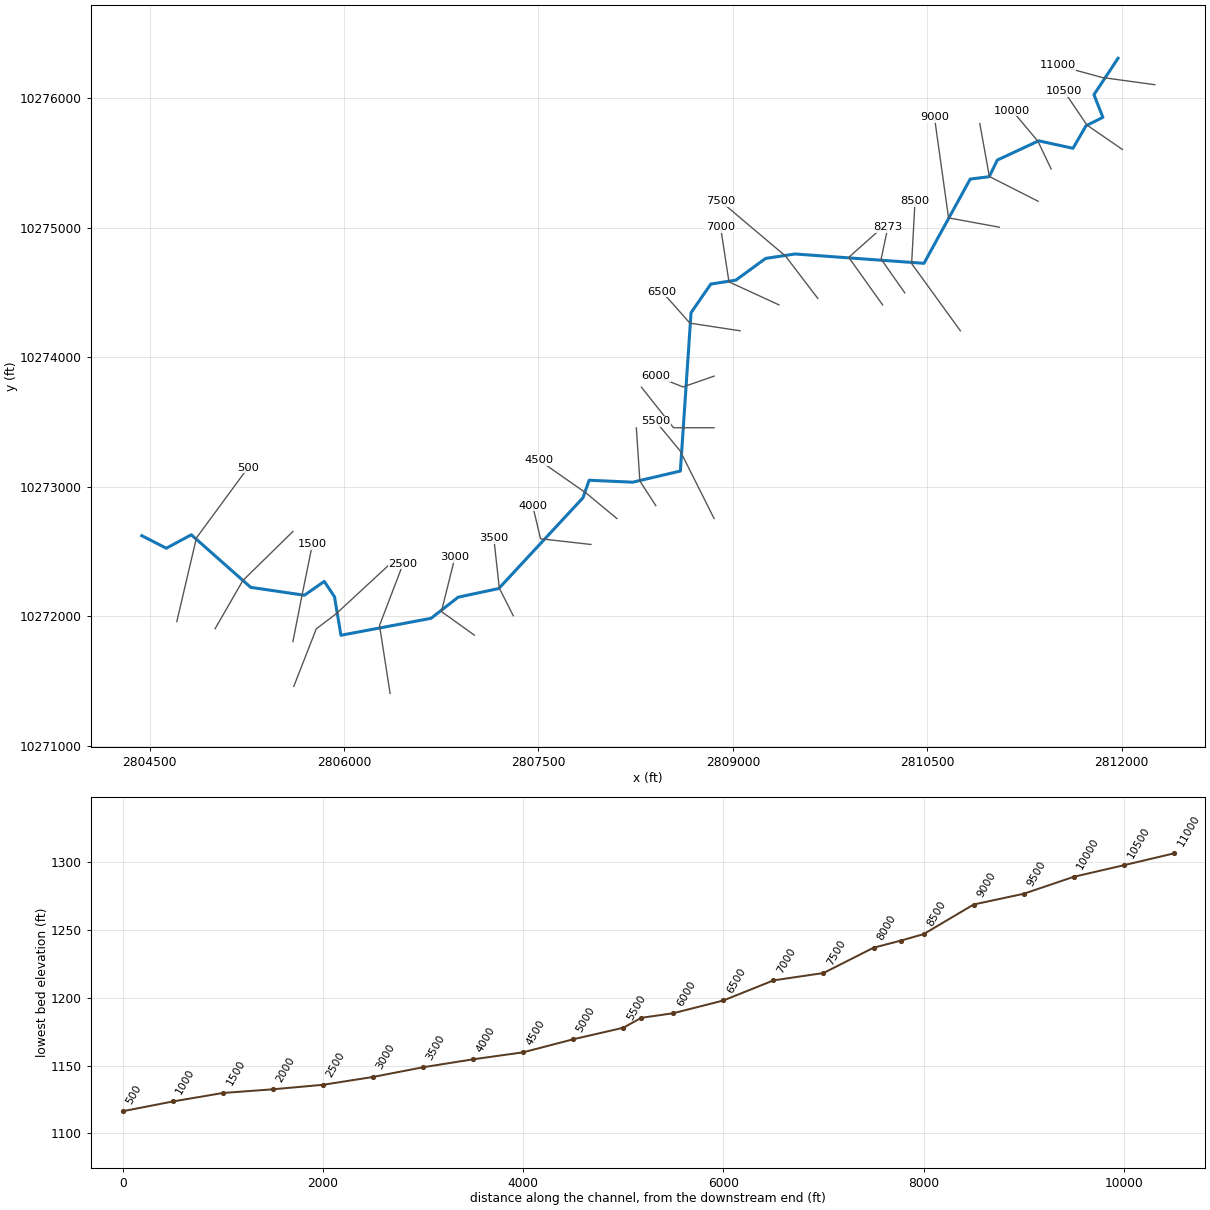
--- SANFERNANDO047.prj (project) ---

Proj Title=SANFERNANDO047 Base Level Engineering
Current Plan=p01
Default Exp/Contr=0.3,0.1
English Units
Geom File=g01
Flow File=f01
Plan File=p01
BEGIN DESCRIPTION:
SANFERNANDO047
END DESCRIPTION:

--- SANFERNANDO047.p01 (plan) ---

Plan Title=Multiple Run
Short Identifier=Multiple
Geom File=g01
Flow File=f01
Subcritical Flow
K Sum by GR= 0
Std Step Tol= 0.01
Critical Tol= 0.01
Num of Std Step Trials= 20
Max Error Tol= 0.3
Flow Tol Ratio= 0.001
Split Flow NTrial= 30
Split Flow Tol= 0.02
Split Flow Ratio= 0.02
Log Output Level= 0
Friction Slope Method= 1
Unsteady Friction Slope Method= 2
Unsteady Bridges Friction Slope Method= 1
Parabolic Critical Depth
Global Vel Dist=  1 , 1 , 1
Global Log Level= 0
CheckData=True
Encroach Param= -1, 0, 0, 0
BEGIN DESCRIPTION:
Multiple Run
END DESCRIPTION:

--- SANFERNANDO047.f01 (steady flow) ---

Flow Title=Multiple
Number of Profiles=7
Profile Names=10-year,25-year,50-year,1pct_min,100-year,1pct_plu,500-year
River Rch & RM= SANFERNANDO047,Reach-1,11000
     442     715    1310     799    1815    4121    2597
River Rch & RM= SANFERNANDO047,Reach-1,2500
     534     878    1553    1069    2158    4355    3079
Boundary for River Rch & Prof#=SANFERNANDO047,Reach-1,1
Up Type=0
Dn Type=3
Dn Slope=0.005
Boundary for River Rch & Prof#=SANFERNANDO047,Reach-1,2
Up Type=0
Dn Type=3
Dn Slope=0.005
Boundary for River Rch & Prof#=SANFERNANDO047,Reach-1,3
Up Type=0
Dn Type=3
Dn Slope=0.005
Boundary for River Rch & Prof#=SANFERNANDO047,Reach-1,4
Up Type=0
Dn Type=3
Dn Slope=0.005
Boundary for River Rch & Prof#=SANFERNANDO047,Reach-1,5
Up Type=0
Dn Type=3
Dn Slope=0.005
Boundary for River Rch & Prof#=SANFERNANDO047,Reach-1,6
Up Type=0
Dn Type=3
Dn Slope=0.005
Boundary for River Rch & Prof#=SANFERNANDO047,Reach-1,7
Up Type=0
Dn Type=3
Dn Slope=0.005

--- SANFERNANDO047.g01 (geometry) ---

Geom Title=Existing Conditions

River Reach=SANFERNANDO047,Reach-1
Reach XY= 30
      2811972.00     10276307.00      2811786.50     10276026.00
      2811855.25     10275851.00      2811725.00     10275786.00
      2811624.75     10275612.00      2811360.25     10275670.00
      2811040.75     10275521.00      2810978.25     10275393.00
      2810831.25     10275374.00      2810475.00     10274724.00
      2809481.00     10274796.00      2809253.25     10274762.00
      2809023.25     10274594.00      2808830.50     10274564.00
      2808677.75     10274343.00      2808595.25     10273120.00
      2808228.00     10273034.00      2807891.50     10273049.00
      2807844.25     10272914.00      2807194.25     10272213.00
      2806880.75     10272146.00      2806671.75     10271983.00
      2805976.50     10271852.00      2805926.75     10272149.00
      2805847.75     10272268.00      2805695.00     10272161.00
      2805280.25     10272222.00      2804821.75     10272628.00
      2804628.75     10272524.00      2804440.00     10272621.00

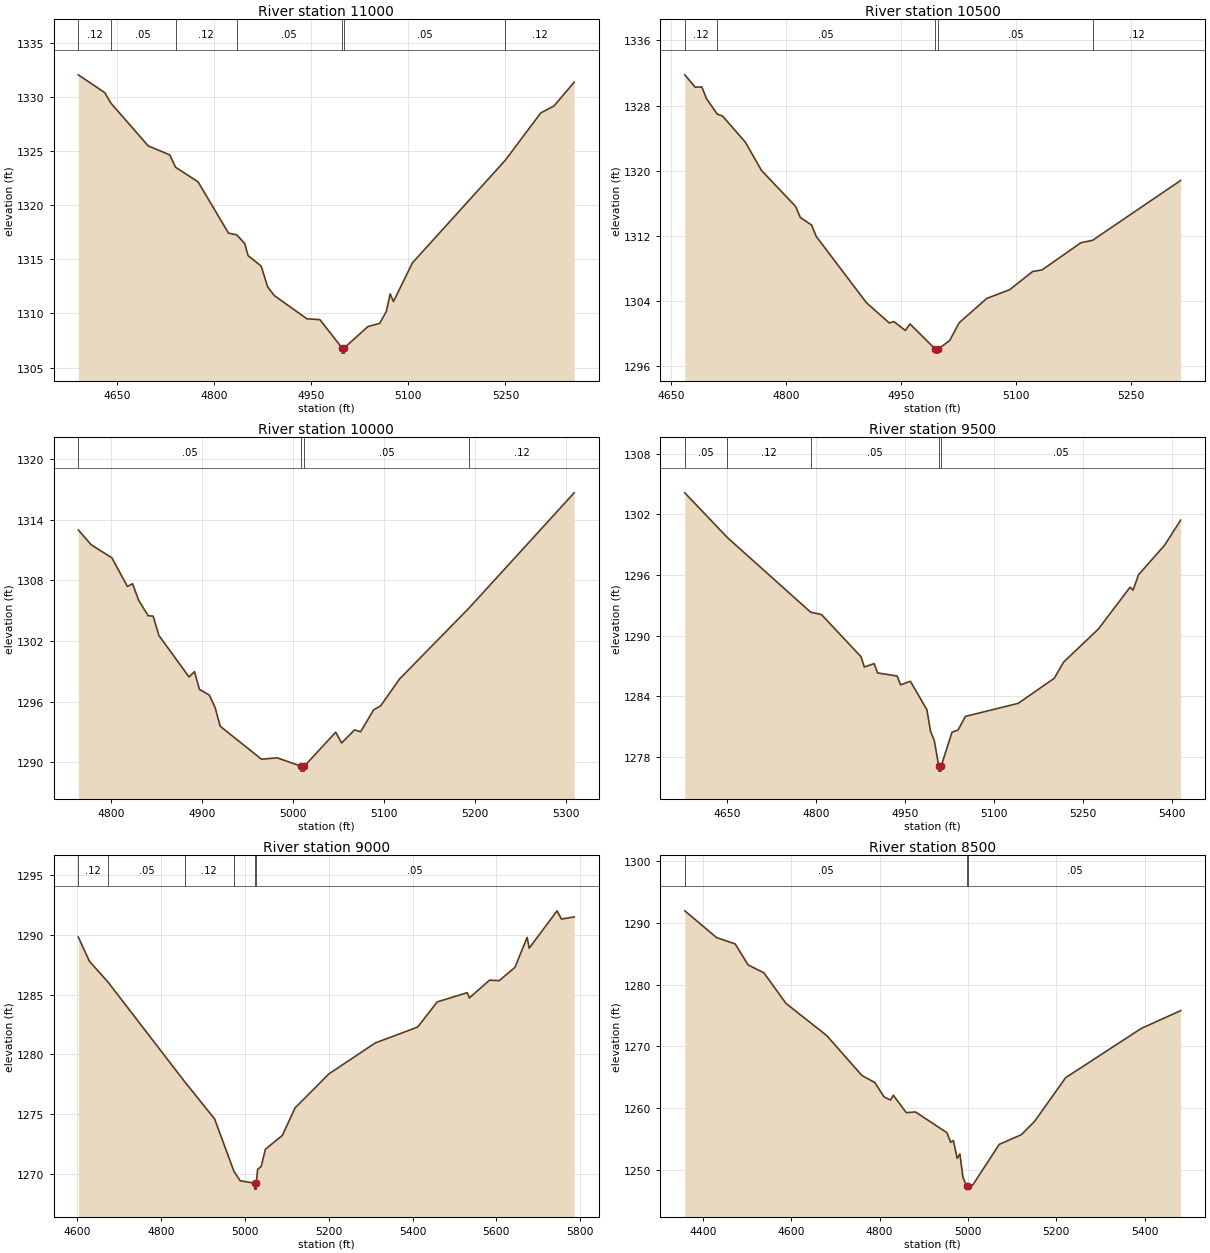
Type RM Length L Ch R = 1,11000,500,500,500
BEGIN DESCRIPTION:
SANFERNANDO047 22.0
END DESCRIPTION:
XS GIS Cut Line= 3
      2812255.65     10276103.12      2811849.37     10276158.95
      2811505.73     10276253.10
#Sta/Elev= 30
  4589.9 1332.03  4630.9 1330.38  4639.9 1329.44  4697.9 1325.47  4731.2 1324.64
  4740.2 1323.50  4775.0 1322.15  4822.0 1317.42  4834.7 1317.26  4847.1 1316.46
  4852.3 1315.34  4872.5 1314.38  4882.6 1312.45  4892.7 1311.66  4943.2 1309.51
  4963.3 1309.43  4997.3 1306.84  4997.6 1306.34  5001.1 1306.34  5001.3 1306.84
  5037.4 1308.79  5055.7 1309.09  5066.0 1310.19  5071.9 1311.81  5077.0 1311.10
  5106.3 1314.67  5249.8 1324.14  5304.6 1328.51  5325.2 1329.16  5356.3 1331.35
#Mann=7,-1,0
  4589.9    0.12       0  4639.9    0.05       0  4740.2    0.12       0
  4834.7    0.05       0  4997.3    0.03       0  5001.3    0.05       0
  5249.8    0.12       0
Bank Sta=4997.3,5001.3
Exp/Cntr=0.3,0.1

Type RM Length L Ch R = 1,10500,500,500,500
BEGIN DESCRIPTION:
SANFERNANDO047 21.0
END DESCRIPTION:
XS GIS Cut Line= 3
      2812005.69     10275603.11      2811732.07     10275791.83
      2811555.71     10276053.08
#Sta/Elev= 30
  4667.6 1331.78  4681.1 1330.27  4689.9 1330.29  4696.0 1328.85  4709.9 1326.97
  4717.0 1326.71  4746.7 1323.52  4767.7 1320.06  4812.3 1315.64  4818.4 1314.29
  4833.3 1313.34  4839.3 1311.95  4904.9 1303.82  4934.7 1301.34  4940.8 1301.51
  4955.7 1300.42  4961.7 1301.22  4994.7 1298.14  4995.0 1297.64  4998.5 1297.64
  4998.7 1298.14  5013.6 1299.19  5026.0 1301.37  5062.0 1304.35  5091.9 1305.42
  5121.9 1307.65  5134.3 1307.85  5184.9 1311.18  5200.2 1311.48  5315.2 1318.82
#Mann=5,-1,0
  4667.6    0.12       0  4709.9    0.05       0  4994.7    0.05       0
  4998.7    0.05       0  5200.2    0.12       0
Bank Sta=4994.7,4998.7
Exp/Cntr=0.3,0.1

Type RM Length L Ch R = 1,10000,500,500,500
BEGIN DESCRIPTION:
SANFERNANDO047 20.0
END DESCRIPTION:
XS GIS Cut Line= 3
      2811455.70     10275453.08      2811354.21     10275666.37
      2811155.66     10275903.14
#Sta/Elev= 30
  4763.8 1313.00  4778.0 1311.53  4800.7 1310.24  4817.8 1307.40  4823.4 1307.67
  4830.3 1306.00  4840.6 1304.50  4846.1 1304.46  4852.4 1302.54  4885.6 1298.43
  4891.5 1298.96  4897.0 1297.20  4907.8 1296.64  4914.2 1295.40  4919.8 1293.55
  4965.2 1290.28  4982.4 1290.42  5008.4 1289.60  5008.7 1289.10  5012.2 1289.10
  5012.4 1289.60  5046.8 1292.96  5053.3 1291.89  5067.6 1293.19  5074.2 1293.00
  5088.5 1295.17  5096.2 1295.57  5117.1 1298.24  5193.7 1305.29  5309.0 1316.68
#Mann=4,-1,0
  4763.8    0.05       0  5008.4    0.05       0  5012.4    0.05       0
  5193.7    0.12       0
Bank Sta=5008.4,5012.4
Exp/Cntr=0.3,0.1

Type RM Length L Ch R = 1,9500,500,500,500
BEGIN DESCRIPTION:
SANFERNANDO047 19.0
END DESCRIPTION:
XS GIS Cut Line= 3
      2811355.68     10275203.11      2810979.40     10275394.38
      2810905.69     10275803.08
#Sta/Elev= 30
  4577.9 1304.12  4649.8 1299.70  4790.5 1292.32  4808.7 1292.09  4875.5 1287.92
  4881.1 1286.90  4897.7 1287.24  4903.4 1286.32  4936.6 1286.01  4942.3 1285.14
  4958.9 1285.49  4986.8 1282.68  4992.9 1280.56  4999.3 1279.63  5006.9 1277.11
  5007.1 1276.61  5010.6 1276.61  5010.9 1277.11  5029.2 1280.46  5039.4 1280.67
  5051.8 1282.02  5141.0 1283.31  5201.9 1285.79  5217.7 1287.39  5276.3 1290.65
  5329.9 1294.79  5335.0 1294.51  5344.2 1296.02  5388.5 1298.96  5415.3 1301.42
#Mann=5,-1,0
  4577.9    0.05       0  4649.8    0.12       0  4790.5    0.05       0
  5006.9    0.05       0  5010.9    0.05       0
Bank Sta=5006.9,5010.9
Exp/Cntr=0.3,0.1

Type RM Length L Ch R = 1,9000,500,500,500
BEGIN DESCRIPTION:
SANFERNANDO047 18.0
END DESCRIPTION:
XS GIS Cut Line= 3
      2811055.73     10275003.10      2810664.36     10275074.89
      2810555.68     10275853.14
#Sta/Elev= 30
  4602.1 1289.82  4628.7 1287.79  4673.4 1286.03  4855.6 1277.72  4927.5 1274.58
  4973.4 1270.21  4988.5 1269.40  5023.0 1269.20  5023.3 1268.70  5026.8 1268.70
  5027.0 1269.20  5030.1 1270.35  5038.6 1270.60  5048.7 1272.04  5089.1 1273.20
  5119.4 1275.50  5200.1 1278.35  5311.0 1280.95  5412.2 1282.28  5459.0 1284.39
  5530.5 1285.16  5535.6 1284.72  5583.8 1286.21  5607.0 1286.17  5644.4 1287.28
  5673.5 1289.79  5678.5 1288.89  5745.0 1292.02  5755.5 1291.33  5785.8 1291.51
#Mann=6,-1,0
  4602.1    0.12       0  4673.4    0.05       0  4855.6    0.12       0
  4973.4    0.05       0  5023.0    0.05       0  5027.0    0.05       0
Bank Sta=5023,5027
Exp/Cntr=0.3,0.1

Type RM Length L Ch R = 1,8500,227,227,227
BEGIN DESCRIPTION:
SANFERNANDO047 17.0
END DESCRIPTION:
XS GIS Cut Line= 3
      2810755.66     10274203.15      2810379.70     10274722.08
      2810405.68     10275203.07
#Sta/Elev= 30
  4359.2 1291.94  4431.5 1287.59  4473.2 1286.59  4502.6 1283.17  4538.2 1281.91
  4588.4 1276.94  4680.4 1271.75  4760.1 1265.28  4789.5 1264.13  4810.4 1261.80
  4825.1 1261.30  4831.2 1262.08  4860.6 1259.26  4881.5 1259.37  4952.6 1256.01
  4961.1 1254.45  4967.3 1254.74  4975.8 1251.85  4982.0 1252.58  4988.9 1248.79
  4997.2 1247.37  4997.4 1246.87  5001.2 1247.37  5011.1 1247.53  5071.1 1254.12
  5121.2 1255.69  5151.3 1257.86  5221.4 1264.92  5392.8 1272.90  5481.7 1275.77
#Mann=3,-1,0
  4359.2    0.05       0  4997.2    0.03       0  5001.2    0.05       0
Bank Sta=4997.2,5001.2
Exp/Cntr=0.3,0.1

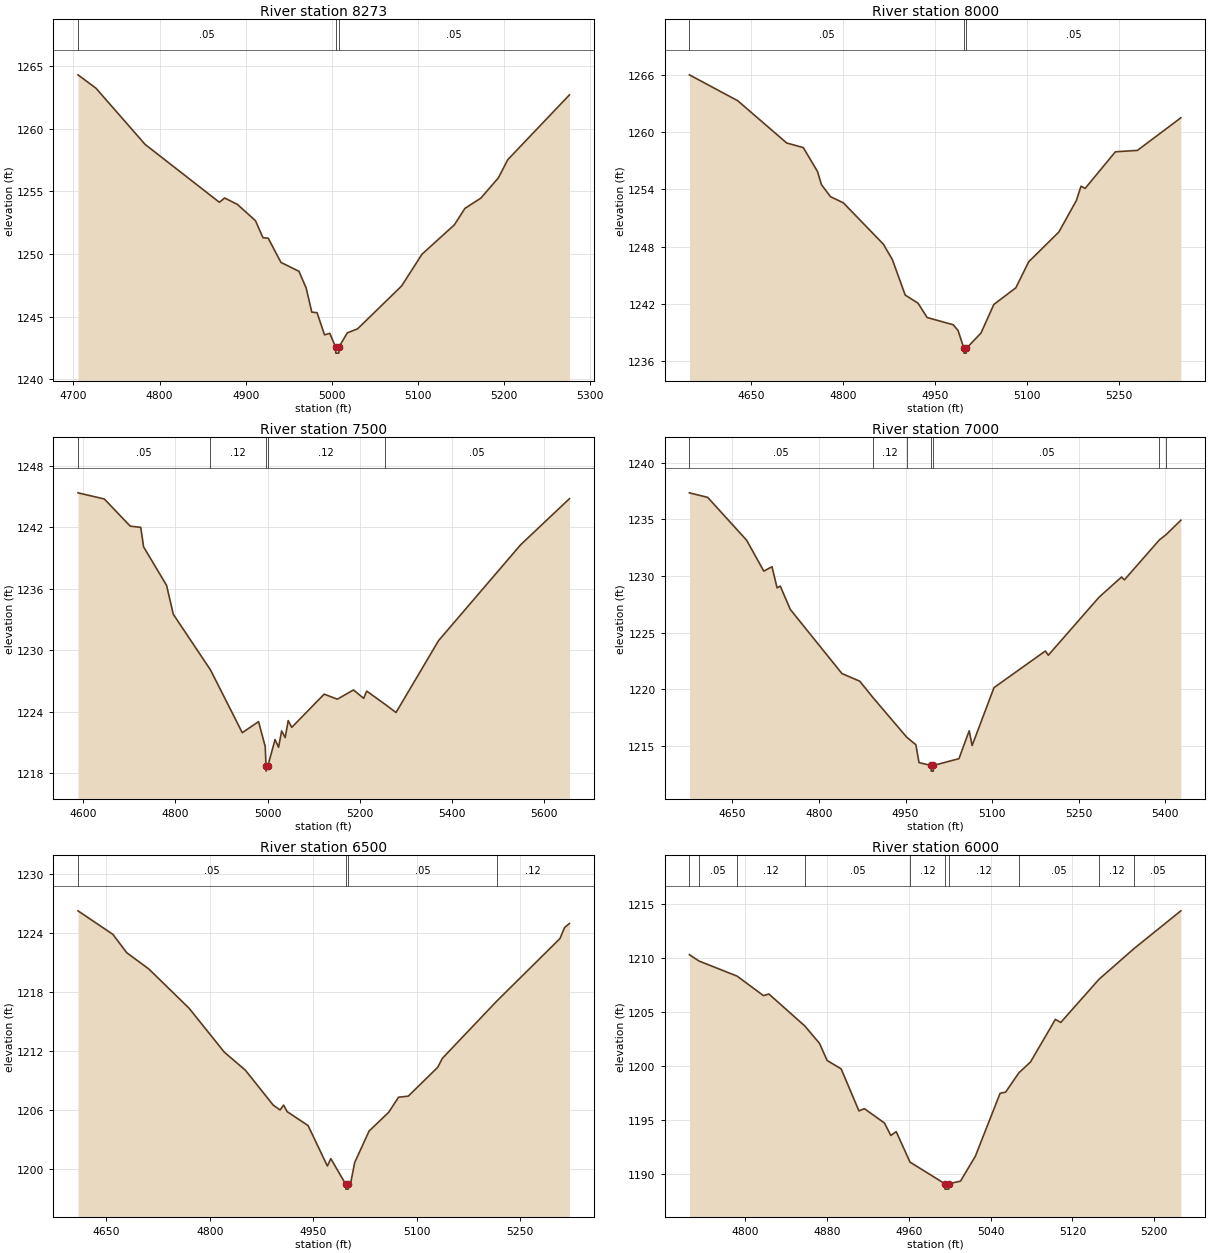
Type RM Length L Ch R = 1,8273,273,273,273
BEGIN DESCRIPTION:
Mapping XS 416ed5f3
END DESCRIPTION:
XS GIS Cut Line= 3
      2810326.57     10274496.03      2810144.27     10274756.45
      2810196.36     10275003.84
#Sta/Elev= 30
  4705.3 1264.31  4726.2 1263.24  4783.2 1258.76  4869.5 1254.14  4875.6 1254.48
  4890.4 1253.97  4911.4 1252.67  4920.1 1251.31  4926.2 1251.27  4941.0 1249.34
  4961.9 1248.63  4970.3 1247.29  4976.8 1245.37  4982.9 1245.33  4991.6 1243.56
  4997.7 1243.68  5004.4 1242.60  5004.7 1242.10  5008.2 1242.10  5008.4 1242.60
  5018.1 1243.72  5030.0 1244.04  5081.1 1247.46  5104.7 1249.99  5142.4 1252.34
  5154.6 1253.65  5173.1 1254.47  5193.5 1256.09  5204.4 1257.54  5276.0 1262.71
#Mann=3,-1,0
  4705.3    0.05       0  5004.4    0.03       0  5008.4    0.05       0
Bank Sta=5004.4,5008.4
Exp/Cntr=0.3,0.1

Type RM Length L Ch R = 1,8000,500,500,500
BEGIN DESCRIPTION:
SANFERNANDO047 16.0
END DESCRIPTION:
XS GIS Cut Line= 3
      2810155.68     10274403.11      2809894.37     10274769.84
      2810155.69     10275003.12
#Sta/Elev= 30
  4549.7 1266.00  4628.4 1263.29  4708.3 1258.86  4735.3 1258.38  4758.4 1255.88
  4764.8 1254.51  4779.6 1253.24  4800.5 1252.60  4865.7 1248.27  4880.4 1246.65
  4901.3 1242.94  4922.2 1242.09  4937.0 1240.59  4979.5 1239.83  4987.4 1239.23
  4996.9 1237.36  4997.2 1236.86  5000.7 1236.86  5000.9 1237.36  5024.7 1238.96
  5045.6 1241.95  5081.5 1243.70  5102.4 1246.42  5151.7 1249.55  5180.2 1252.85
  5187.7 1254.34  5194.4 1254.11  5243.7 1257.94  5279.6 1258.09  5350.3 1261.50
#Mann=3,-1,0
  4549.7    0.05       0  4996.9    0.03       0  5000.9    0.05       0
Bank Sta=4996.9,5000.9
Exp/Cntr=0.3,0.1

Type RM Length L Ch R = 1,7500,500,500,500
BEGIN DESCRIPTION:
SANFERNANDO047 15.0
END DESCRIPTION:
XS GIS Cut Line= 3
      2809655.70     10274453.09      2809406.30     10274780.40
      2808905.69     10275203.10
#Sta/Elev= 30
  4588.5 1245.37  4645.7 1244.77  4701.9 1242.12  4724.7 1242.00  4730.9 1240.10
  4780.8 1236.34  4795.4 1233.52  4876.0 1228.10  4945.1 1221.97  4980.4 1223.05
  4994.9 1220.62  4996.6 1218.72  4996.8 1218.22  5000.6 1218.72  5016.2 1221.30
  5023.9 1220.55  5030.5 1222.14  5038.2 1221.49  5044.8 1223.15  5052.5 1222.49
  5122.8 1225.73  5151.4 1225.24  5186.5 1226.14  5208.6 1225.32  5215.1 1226.03
  5254.1 1224.77  5278.8 1223.94  5371.1 1230.95  5549.2 1240.30  5655.2 1244.80
#Mann=5,-1,0
  4588.5    0.05       0  4876.0    0.12       0  4996.6    0.07       0
  5000.6    0.12       0  5254.1    0.05       0
Bank Sta=4996.6,5000.6
Exp/Cntr=0.3,0.1

Type RM Length L Ch R = 1,7000,500,500,500
BEGIN DESCRIPTION:
SANFERNANDO047 14.0
END DESCRIPTION:
XS GIS Cut Line= 3
      2809355.73     10274403.09      2808970.18     10274580.95
      2808905.68     10275003.15
#Sta/Elev= 30
  4575.4 1237.35  4607.1 1236.95  4674.6 1233.17  4704.4 1230.44  4718.6 1230.83
  4727.4 1228.96  4732.9 1229.12  4750.3 1227.06  4839.8 1221.40  4870.6 1220.73
  4893.6 1219.28  4952.3 1215.77  4967.9 1215.12  4973.4 1213.54  4994.3 1213.29
  4994.6 1212.79  4998.1 1212.79  4998.3 1213.29  5042.6 1213.89  5060.3 1216.35
  5065.4 1215.05  5103.3 1220.16  5192.3 1223.39  5197.4 1223.02  5285.4 1228.14
  5324.3 1229.92  5329.3 1229.67  5390.0 1233.20  5401.1 1233.64  5427.1 1234.93
#Mann=7,-1,0
  4575.4    0.05       0  4893.6    0.12       0  4952.3    0.05       0
  4994.3    0.05       0  4998.3    0.05       0  5390.0    0.12       0
  5401.1    0.05       0
Bank Sta=4994.3,4998.3
Exp/Cntr=0.3,0.1

Type RM Length L Ch R = 1,6500,500,500,500
BEGIN DESCRIPTION:
SANFERNANDO047 13.0
END DESCRIPTION:
XS GIS Cut Line= 3
      2809055.69     10274203.11      2808668.87     10274262.17
      2808455.69     10274503.10
#Sta/Elev= 30
  4608.7 1226.26  4659.3 1223.87  4679.5 1222.00  4711.5 1220.35  4769.9 1216.36
  4821.1 1211.89  4851.5 1210.07  4891.9 1206.52  4901.9 1206.02  4907.0 1206.52
  4912.2 1205.85  4942.5 1204.44  4970.5 1200.33  4975.5 1201.08  4997.1 1198.48
  4997.3 1197.98  5000.8 1197.98  5001.1 1198.48  5004.0 1198.48  5010.1 1200.68
  5031.0 1203.88  5059.5 1205.79  5073.7 1207.32  5087.9 1207.43  5130.6 1210.36
  5137.3 1211.27  5216.3 1217.09  5307.9 1223.44  5314.6 1224.56  5321.7 1224.97
#Mann=4,-1,0
  4608.7    0.05       0  4997.1    0.05       0  5001.1    0.05       0
  5216.3    0.12       0
Bank Sta=4997.1,5001.1
Exp/Cntr=0.3,0.1

Type RM Length L Ch R = 1,6000,320,320,320
BEGIN DESCRIPTION:
SANFERNANDO047 12.0
END DESCRIPTION:
XS GIS Cut Line= 3
      2808855.71     10273853.12      2808615.56     10273769.46
      2808405.72     10273853.10
#Sta/Elev= 30
  4745.7 1210.31  4755.2 1209.72  4792.3 1208.33  4818.1 1206.52  4823.4 1206.67
  4858.3 1203.73  4872.8 1202.11  4880.3 1200.52  4894.0 1199.74  4911.4 1195.85
  4916.7 1196.06  4936.3 1194.73  4942.5 1193.58  4947.8 1193.93  4961.3 1191.11
  4995.3 1189.11  4995.5 1188.61  4999.0 1188.61  4999.3 1189.11  5010.6 1189.35
  5025.1 1191.65  5049.3 1197.48  5054.7 1197.59  5067.6 1199.37  5079.0 1200.38
  5103.3 1204.32  5108.6 1204.04  5146.0 1208.04  5180.1 1210.87  5225.9 1214.37
#Mann=10,-1,0
  4745.7    0.12       0  4755.2    0.05       0  4792.3    0.12       0
  4858.3    0.05       0  4961.3    0.12       0  4995.3    0.07       0
  4999.3    0.12       0  5067.6    0.05       0  5146.0    0.12       0
  5180.1    0.05       0
Bank Sta=4995.3,4999.3
Exp/Cntr=0.3,0.1

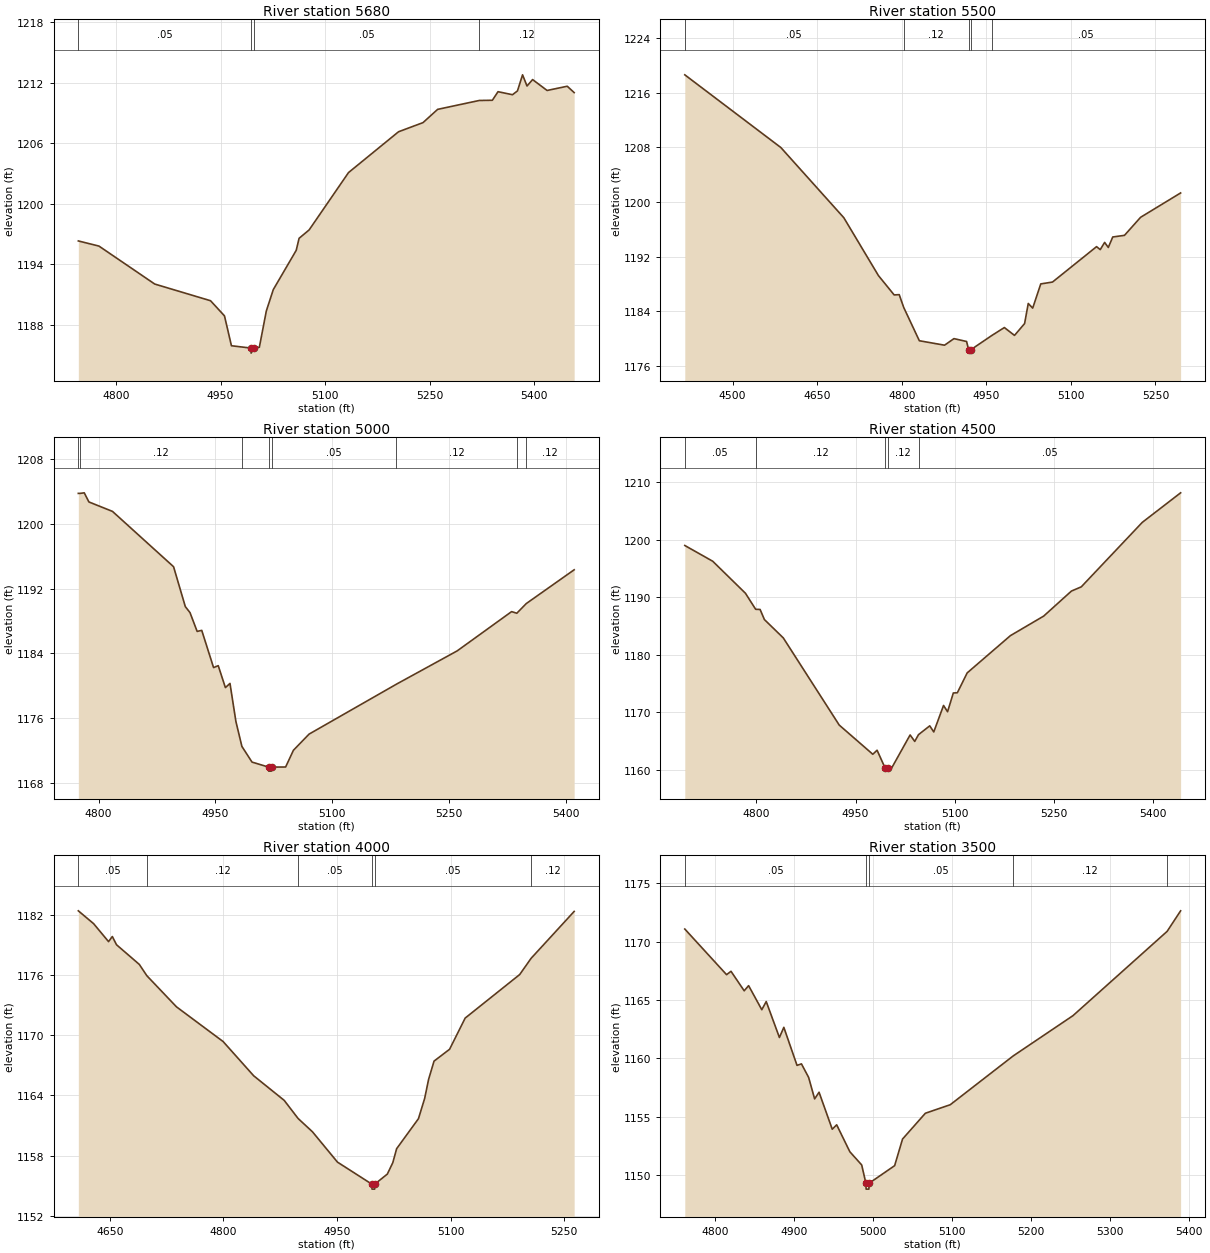
Type RM Length L Ch R = 1,5680,180,180,180
BEGIN DESCRIPTION:
Mapping XS 949bb1ca
END DESCRIPTION:
XS GIS Cut Line= 3
      2808855.25     10273454.37      2808542.71     10273454.37
      2808295.32     10273766.86
#Sta/Elev= 30
  4746.0 1196.32  4775.6 1195.81  4855.6 1192.05  4935.6 1190.40  4955.6 1188.90
  4965.6 1185.94  4993.6 1185.71  4993.8 1185.21  4997.6 1185.71  5005.6 1185.79
  5015.6 1189.38  5025.6 1191.50  5058.5 1195.39  5062.6 1196.58  5077.0 1197.41
  5133.5 1203.09  5205.2 1207.13  5240.4 1208.04  5261.3 1209.35  5321.0 1210.23
  5339.8 1210.25  5347.9 1211.10  5368.7 1210.80  5375.8 1211.18  5383.1 1212.77
  5389.5 1211.66  5397.5 1212.30  5418.3 1211.22  5447.2 1211.64  5457.1 1211.01
#Mann=4,-1,0
  4746.0    0.05       0  4993.6    0.05       0  4997.6    0.05       0
  5321.0    0.12       0
Bank Sta=4993.6,4997.6
Exp/Cntr=0.3,0.1

Type RM Length L Ch R = 1,5500,500,500,500
BEGIN DESCRIPTION:
SANFERNANDO047 11.0
END DESCRIPTION:
XS GIS Cut Line= 3
      2808855.69     10272753.11      2808593.46     10273275.93
      2808405.71     10273503.08
#Sta/Elev= 30
  4415.1 1218.60  4585.5 1207.97  4697.2 1197.71  4758.6 1189.25  4786.5 1186.42
  4795.5 1186.46  4803.4 1184.60  4831.2 1179.72  4875.9 1179.07  4892.6 1180.03
  4915.0 1179.61  4918.6 1178.41  4918.8 1177.91  4922.6 1178.41  4959.6 1180.48
  4982.0 1181.65  5000.0 1180.50  5017.9 1182.23  5024.4 1185.17  5032.3 1184.49
  5046.6 1188.03  5067.4 1188.30  5145.6 1193.48  5152.1 1193.04  5159.9 1194.10
  5166.4 1193.36  5174.3 1194.89  5195.1 1195.13  5223.7 1197.77  5294.7 1201.33
#Mann=5,-1,0
  4415.1    0.05       0  4803.4    0.12       0  4918.6    0.05       0
  4922.6    0.12       0  4959.6    0.05       0
Bank Sta=4918.6,4922.6
Exp/Cntr=0.3,0.1

Type RM Length L Ch R = 1,5000,500,500,500
BEGIN DESCRIPTION:
SANFERNANDO047 10.0
END DESCRIPTION:
XS GIS Cut Line= 3
      2808405.70     10272853.09      2808282.84     10273042.90
      2808255.68     10273453.10
#Sta/Elev= 30
  4773.9 1203.80  4776.1 1203.80  4781.5 1203.87  4787.5 1202.74  4817.8 1201.57
  4896.3 1194.72  4911.4 1189.78  4917.4 1189.04  4926.6 1186.71  4932.5 1186.84
  4947.7 1182.23  4953.7 1182.47  4962.9 1179.75  4968.8 1180.27  4976.4 1175.56
  4984.1 1172.47  4997.1 1170.53  5018.3 1169.91  5018.5 1169.41  5022.0 1169.41
  5022.3 1169.91  5040.3 1169.92  5050.3 1171.99  5070.4 1173.99  5182.6 1180.17
  5260.8 1184.30  5330.7 1189.16  5337.4 1188.96  5349.6 1190.16  5411.1 1194.34
#Mann=8,-1,0
  4773.9    0.05       0  4776.1    0.12       0  4984.1    0.05       0
  5018.3    0.05       0  5022.3    0.05       0  5182.6    0.12       0
  5337.4    0.05       0  5349.6    0.12       0
Bank Sta=5018.3,5022.3
Exp/Cntr=0.3,0.1

Type RM Length L Ch R = 1,4500,500,500,500
BEGIN DESCRIPTION:
SANFERNANDO047 9.0
END DESCRIPTION:
XS GIS Cut Line= 3
      2808105.69     10272753.11      2807868.14     10272949.94
      2807505.70     10273203.10
#Sta/Elev= 30
  4691.5 1199.02  4733.8 1196.28  4783.3 1190.72  4798.8 1187.93  4805.5 1187.90
  4812.0 1186.15  4840.6 1182.96  4925.3 1167.81  4976.1 1162.74  4982.6 1163.44
  4994.9 1160.31  4995.2 1159.81  4998.9 1160.31  5004.5 1160.32  5032.6 1166.10
  5039.6 1164.97  5045.3 1166.15  5062.3 1167.68  5068.4 1166.62  5083.2 1171.22
  5089.3 1170.13  5098.0 1173.39  5104.1 1173.43  5119.0 1176.88  5184.4 1183.35
  5234.8 1186.75  5276.8 1191.10  5291.7 1191.83  5384.1 1203.04  5442.1 1208.17
#Mann=5,-1,0
  4691.5    0.05       0  4798.8    0.12       0  4994.9    0.07       0
  4998.9    0.12       0  5045.3    0.05       0
Bank Sta=4994.9,4998.9
Exp/Cntr=0.3,0.1

Type RM Length L Ch R = 1,4000,500,500,500
BEGIN DESCRIPTION:
SANFERNANDO047 8.0
END DESCRIPTION:
XS GIS Cut Line= 3
      2807905.72     10272553.11      2807516.60     10272597.14
      2807455.69     10272853.10
#Sta/Elev= 30
  4608.4 1182.39  4628.6 1181.11  4648.3 1179.32  4653.3 1179.83  4658.8 1179.01
  4688.9 1177.05  4698.9 1175.92  4738.0 1172.82  4799.6 1169.36  4839.9 1165.95
  4880.2 1163.50  4898.6 1161.69  4917.5 1160.37  4950.6 1157.34  4995.9 1155.15
  4996.2 1154.65  4999.7 1154.65  4999.9 1155.15  5016.4 1156.15  5023.6 1157.28
  5028.7 1158.68  5057.5 1161.67  5065.7 1163.69  5070.9 1165.59  5078.1 1167.41
  5098.6 1168.59  5119.2 1171.70  5191.2 1176.04  5206.2 1177.65  5263.1 1182.33
#Mann=6,-1,0
  4608.4    0.05       0  4698.9    0.12       0  4898.6    0.05       0
  4995.9    0.05       0  4999.9    0.05       0  5206.2    0.12       0
Bank Sta=4995.9,4999.9
Exp/Cntr=0.3,0.1

Type RM Length L Ch R = 1,3500,500,500,500
BEGIN DESCRIPTION:
SANFERNANDO047 7.0
END DESCRIPTION:
XS GIS Cut Line= 3
      2807305.66     10272003.15      2807198.37     10272215.82
      2807155.69     10272603.07
#Sta/Elev= 30
  4761.8 1171.07  4814.7 1167.16  4820.3 1167.45  4837.0 1165.78  4842.6 1166.22
  4859.3 1164.16  4864.9 1164.86  4881.6 1161.78  4887.2 1162.65  4903.9 1159.39
  4909.5 1159.52  4918.6 1158.36  4926.2 1156.52  4931.8 1157.09  4948.5 1153.92
  4954.1 1154.30  4970.8 1151.99  4985.8 1150.86  4991.1 1149.29  4991.4 1148.79
  4994.9 1148.79  4995.1 1149.29  5027.5 1150.80  5037.5 1153.08  5066.4 1155.29
  5097.9 1156.02  5177.6 1160.20  5253.3 1163.65  5372.5 1170.87  5389.6 1172.63
#Mann=5,-1,0
  4761.8    0.05       0  4991.1    0.05       0  4995.1    0.05       0
  5177.6    0.12       0  5372.5    0.05       0
Bank Sta=4991.1,4995.1
Exp/Cntr=0.3,0.1

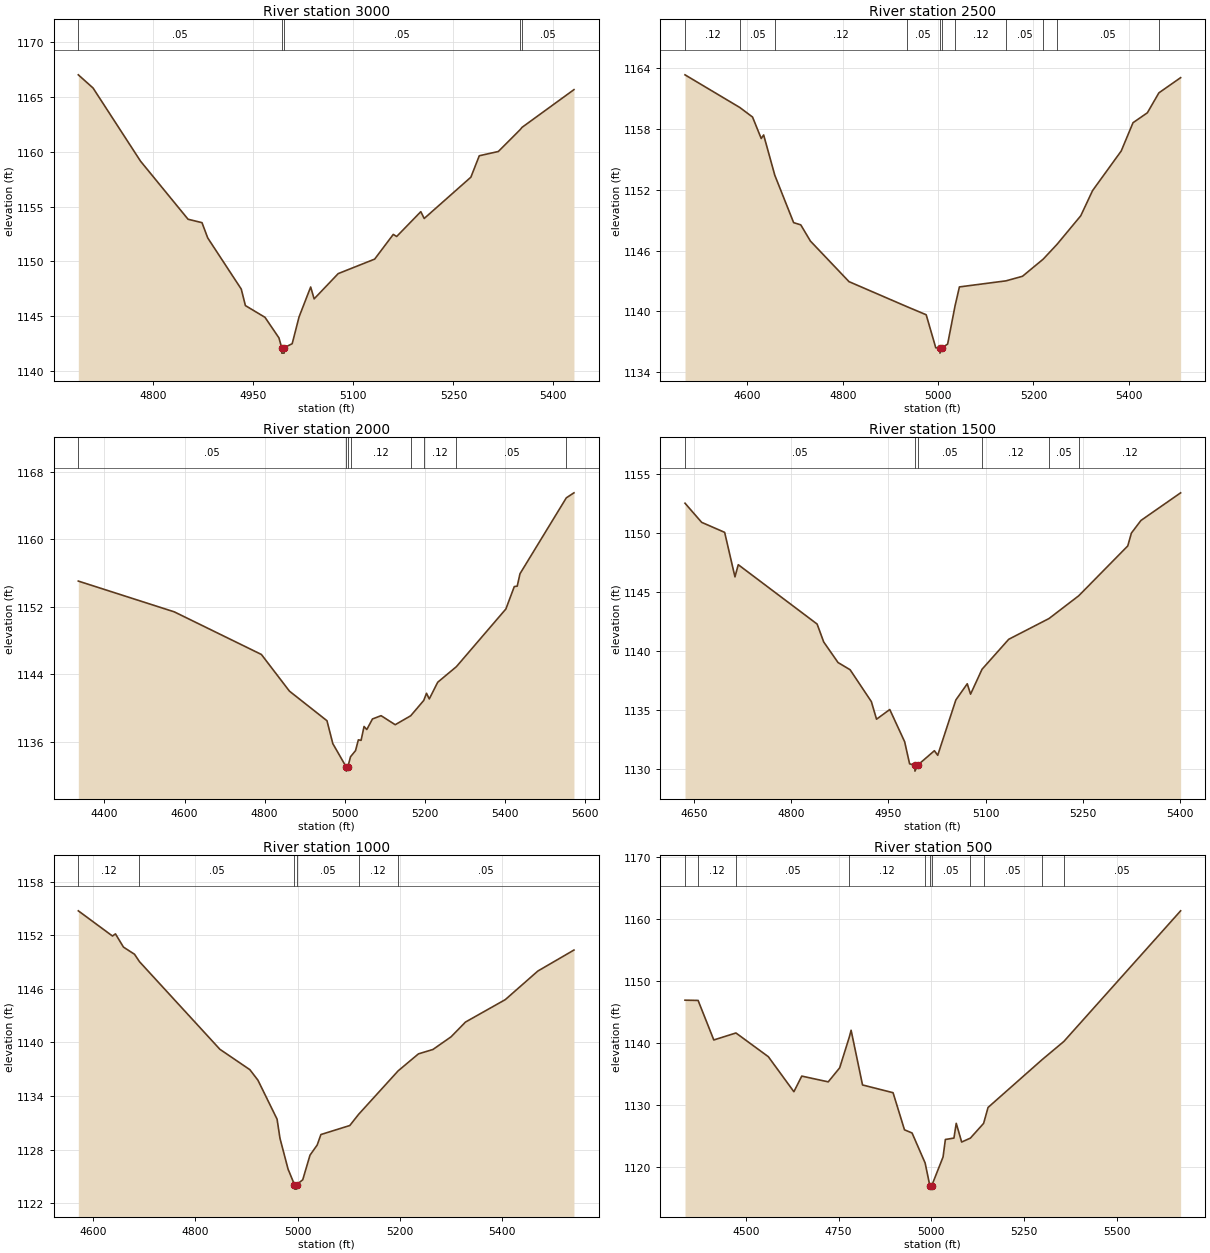
Type RM Length L Ch R = 1,3000,500,500,500
BEGIN DESCRIPTION:
SANFERNANDO047 6.0
END DESCRIPTION:
XS GIS Cut Line= 3
      2807005.67     10271853.12      2806751.53     10272035.14
      2806855.70     10272453.16
#Sta/Elev= 30
  4687.4 1166.99  4709.5 1165.79  4780.7 1159.13  4852.0 1153.84  4872.9 1153.53
  4881.5 1152.14  4931.8 1147.48  4938.0 1145.98  4967.4 1144.91  4988.3 1143.04
  4992.4 1142.15  4992.6 1141.65  4996.1 1141.65  4996.4 1142.15  5008.2 1142.51
  5018.5 1144.95  5035.9 1147.67  5041.1 1146.59  5077.2 1148.89  5131.9 1150.21
  5159.8 1152.46  5164.9 1152.27  5201.1 1154.53  5206.2 1153.91  5276.2 1157.67
  5288.8 1159.62  5317.4 1160.01  5350.3 1162.01  5353.0 1162.21  5430.8 1165.64
#Mann=5,-1,0
  4687.4    0.05       0  4992.4    0.03       0  4996.4    0.05       0
  5350.3    0.12       0  5353.0    0.05       0
Bank Sta=4992.4,4996.4
Exp/Cntr=0.3,0.1

Type RM Length L Ch R = 1,2500,500,500,500
BEGIN DESCRIPTION:
SANFERNANDO047 5.0
END DESCRIPTION:
XS GIS Cut Line= 3
      2806355.69     10271403.08      2806274.19     10271927.79
      2806455.69     10272403.11
#Sta/Elev= 30
  4469.0 1163.36  4584.1 1160.13  4610.7 1159.19  4628.9 1157.07  4634.0 1157.42
  4657.4 1153.44  4696.9 1148.76  4711.9 1148.54  4732.1 1146.94  4813.1 1142.93
  4934.1 1140.47  4975.0 1139.66  4995.1 1136.40  5003.6 1136.37  5003.9 1135.87
  5007.8 1136.37  5020.0 1136.77  5035.6 1140.55  5044.7 1142.41  5142.5 1143.01
  5177.0 1143.46  5220.4 1145.15  5249.4 1146.61  5299.3 1149.44  5324.0 1151.92
  5384.2 1155.84  5408.9 1158.63  5439.0 1159.61  5463.2 1161.58  5508.8 1163.08
#Mann=11,-1,0
  4469.0    0.12       0  4584.1    0.05       0  4657.4    0.12       0
  4934.1    0.05       0  5003.6    0.05       0  5007.8    0.05       0
  5035.6    0.12       0  5142.5    0.05       0  5220.4    0.12       0
  5249.4    0.05       0  5463.2    0.12       0
Bank Sta=5003.6,5007.8
Exp/Cntr=0.3,0.1

Type RM Length L Ch R = 1,2000,500,500,500
BEGIN DESCRIPTION:
SANFERNANDO047 4.0
END DESCRIPTION:
XS GIS Cut Line= 4
      2805612.71     10271457.54      2805786.23     10271902.07
      2805936.17     10272015.00      2806355.68     10272403.10
#Sta/Elev= 30
  4335.1 1155.04  4574.5 1151.40  4791.8 1146.36  4861.8 1142.02  4955.4 1138.52
  4970.0 1135.81  5003.3 1133.06  5003.6 1132.56  5007.5 1133.06  5014.1 1134.26
  5026.6 1134.98  5033.7 1136.26  5040.5 1136.20  5047.9 1137.84  5054.7 1137.48
  5068.9 1138.73  5090.4 1139.12  5125.6 1138.05  5164.3 1139.11  5196.8 1140.92
  5203.7 1141.77  5210.6 1141.10  5231.6 1143.07  5278.3 1144.92  5401.7 1151.74
  5422.7 1154.39  5430.0 1154.44  5436.9 1155.91  5552.5 1164.89  5571.5 1165.48
#Mann=8,-1,0
  4335.1    0.05       0  5003.3    0.05       0  5007.5    0.05       0
  5014.1    0.12       0  5164.3    0.05       0  5196.8    0.12       0
  5278.3    0.05       0  5552.5    0.12       0
Bank Sta=5003.3,5007.5
Exp/Cntr=0.3,0.1

Type RM Length L Ch R = 1,1500,500,500,500
BEGIN DESCRIPTION:
SANFERNANDO047 3.0
END DESCRIPTION:
XS GIS Cut Line= 3
      2805605.68     10271803.08      2805675.98     10272160.13
      2805755.69     10272553.12
#Sta/Elev= 30
  4636.1 1152.54  4661.8 1150.92  4697.3 1150.07  4713.2 1146.30  4718.3 1147.33
  4840.0 1142.30  4850.2 1140.78  4872.3 1139.04  4890.9 1138.43  4923.7 1135.73
  4931.7 1134.24  4952.1 1135.06  4975.1 1132.33  4982.7 1130.46  4990.7 1130.34
  4991.0 1129.84  4995.1 1130.34  5021.0 1131.57  5026.1 1131.18  5054.1 1135.87
  5071.7 1137.24  5076.8 1136.36  5094.5 1138.47  5135.7 1141.01  5197.9 1142.77
  5243.8 1144.70  5319.4 1148.92  5325.0 1150.01  5339.8 1151.08  5401.0 1153.42
#Mann=6,-1,0
  4636.1    0.05       0  4990.7    0.05       0  4995.1    0.05       0
  5094.5    0.12       0  5197.9    0.05       0  5243.8    0.12       0
Bank Sta=4990.7,4995.1
Exp/Cntr=0.3,0.1

Type RM Length L Ch R = 1,1000,500,500,500
BEGIN DESCRIPTION:
SANFERNANDO047 2.0
END DESCRIPTION:
XS GIS Cut Line= 3
      2805005.69     10271903.12      2805219.61     10272274.64
      2805605.65     10272653.08
#Sta/Elev= 30
  4571.3 1154.73  4638.1 1151.91  4643.9 1152.15  4659.6 1150.67  4681.2 1149.87
  4690.9 1149.04  4848.2 1139.23  4906.8 1136.95  4922.6 1135.77  4960.0 1131.41
  4965.7 1129.26  4981.5 1125.82  4994.0 1124.08  4994.3 1123.58  4998.1 1123.58
  4998.4 1124.08  5010.2 1124.63  5024.4 1127.38  5038.5 1128.52  5045.7 1129.69
  5102.2 1130.70  5119.3 1131.94  5196.8 1136.82  5236.5 1138.72  5264.8 1139.21
  5300.3 1140.63  5328.5 1142.28  5406.3 1144.79  5470.0 1147.99  5540.6 1150.34
#Mann=6,-1,0
  4571.3    0.12       0  4690.9    0.05       0  4994.0    0.05       0
  4998.4    0.05       0  5119.3    0.12       0  5196.8    0.05       0
Bank Sta=4994,4998.4
Exp/Cntr=0.3,0.1

Type RM Length L Ch R = 1,500,0,0,0
BEGIN DESCRIPTION:
SANFERNANDO047 1.0
END DESCRIPTION:
XS GIS Cut Line= 3
      2804709.93     10271957.53      2804861.39     10272603.51
      2805258.52     10273144.99
#Sta/Elev= 30
  4336.5 1146.89  4371.8 1146.85  4414.1 1140.47  4473.7 1141.60  4561.0 1137.77
  4629.8 1132.12  4651.0 1134.64  4722.3 1133.71  4753.1 1135.97  4779.5 1141.02
  4783.9 1142.04  4814.7 1133.21  4896.9 1131.96  4927.7 1125.97  4948.1 1125.46
  4983.3 1120.62  4996.2 1116.90  4996.5 1116.40  5000.7 1116.90  5031.6 1121.59
  5037.8 1124.41  5060.9 1124.64  5067.1 1127.02  5081.7 1124.00  5105.2 1124.63
  5140.8 1127.01  5152.8 1129.58  5298.5 1137.30  5356.8 1140.22  5671.5 1161.31
#Mann=11,-1,0
  4336.5    0.05       0  4371.8    0.12       0  4473.7    0.05       0
  4779.5    0.12       0  4983.3    0.05       0  4996.2    0.05       0
  5000.7    0.05       0  5105.2    0.12       0  5140.8    0.05       0
  5298.5    0.12       0  5356.8    0.05       0
Bank Sta=4996.2,5000.7
Exp/Cntr=0.3,0.1

Chan Stop Cuts=-1