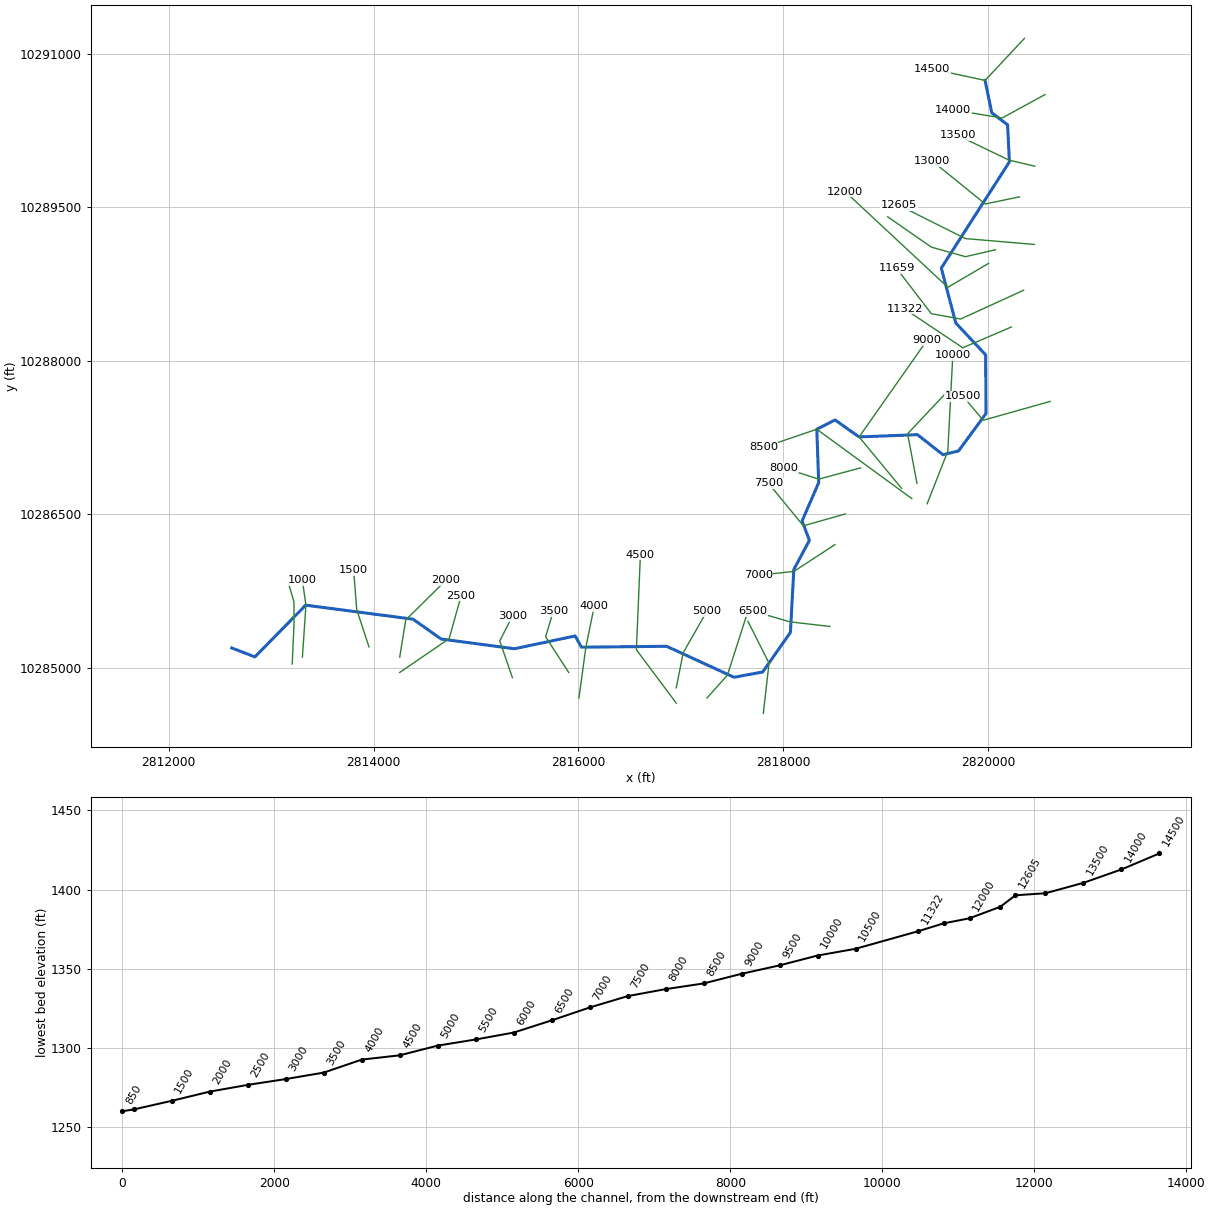
--- SANFERNANDO049.prj (project) ---

Proj Title=SANFERNANDO049 Base Level Engineering
Current Plan=p01
Default Exp/Contr=0.3,0.1
English Units
Geom File=g01
Flow File=f01
Plan File=p01
Y Axis Title=Elevation
X Axis Title(PF)=Main Channel Distance
X Axis Title(XS)=Station
BEGIN DESCRIPTION:
SANFERNANDO049
END DESCRIPTION:
DSS Export Rating Curves= 0
DSS Export Rating Curve Sorted= 0
DSS Export Volume Flow Curves= 0
DXF OffsetX= 0
DXF OffsetY= 0
DXF ScaleX= 1
DXF ScaleY= 10

--- SANFERNANDO049.p01 (plan) ---

Plan Title=Multiple Run
Short Identifier=Multiple
Geom File=g01
Flow File=f01
Subcritical Flow
K Sum by GR= 0
Std Step Tol= 0.01
Critical Tol= 0.01
Num of Std Step Trials= 20
Max Error Tol= 0.3
Flow Tol Ratio= 0.001
Split Flow NTrial= 30
Split Flow Tol= 0.02
Split Flow Ratio= 0.02
Log Output Level= 0
Friction Slope Method= 1
Unsteady Friction Slope Method= 2
Unsteady Bridges Friction Slope Method= 1
Parabolic Critical Depth
Global Vel Dist=  1 , 1 , 1
Global Log Level= 0
CheckData=True
Encroach Param= -1, 0, 0, 0
BEGIN DESCRIPTION:
Multiple Run
END DESCRIPTION:

--- SANFERNANDO049.f01 (steady flow) ---

Flow Title=Multiple
Number of Profiles=7
Profile Names=10-year,25-year,50-year,1pct_min,100-year,1pct_plu,500-year
River Rch & RM= SANFERNANDO049,Reach-1,14500
     486     796    1396     870    1937    4315    2777
River Rch & RM= SANFERNANDO049,Reach-1,3000
     629    1050    1822    1332    2547    4867    3639
Boundary for River Rch & Prof#=SANFERNANDO049,Reach-1,1
Up Type=0
Dn Type=3
Dn Slope=0.005
Boundary for River Rch & Prof#=SANFERNANDO049,Reach-1,2
Up Type=0
Dn Type=3
Dn Slope=0.005
Boundary for River Rch & Prof#=SANFERNANDO049,Reach-1,3
Up Type=0
Dn Type=3
Dn Slope=0.005
Boundary for River Rch & Prof#=SANFERNANDO049,Reach-1,4
Up Type=0
Dn Type=3
Dn Slope=0.005
Boundary for River Rch & Prof#=SANFERNANDO049,Reach-1,5
Up Type=0
Dn Type=3
Dn Slope=0.005
Boundary for River Rch & Prof#=SANFERNANDO049,Reach-1,6
Up Type=0
Dn Type=3
Dn Slope=0.005
Boundary for River Rch & Prof#=SANFERNANDO049,Reach-1,7
Up Type=0
Dn Type=3
Dn Slope=0.005

--- SANFERNANDO049.g01 (geometry) ---

Geom Title=Existing Conditions
Program Version=4.10

River Reach=SANFERNANDO049  ,Reach-1
Reach XY= 30
       2819970.5       10290742.        2820036.       10290425.
      2820190.75       10290308.      2820208.25       10289945.
      2819543.25       10288907.      2819684.75       10288370.
      2819976.75       10288058.       2819979.5       10287484.
      2819711.75       10287119.       2819559.5       10287082.
       2819310.5       10287278.      2818740.25       10287256.
        2818506.       10287422.      2818327.75       10287331.
       2818346.5       10286809.        2818184.       10286434.
      2818255.75       10286245.       2818103.5       10285960.
      2818070.25       10285345.        2817800.       10284958.
        2817520.       10284906.       2816861.5       10285209.
        2816030.       10285200.       2815968.5       10285310.
       2815375.5       10285185.      2814660.25       10285280.
        2814386.       10285474.       2813337.5       10285611.
      2812841.75       10285105.      2812615.75       10285193.

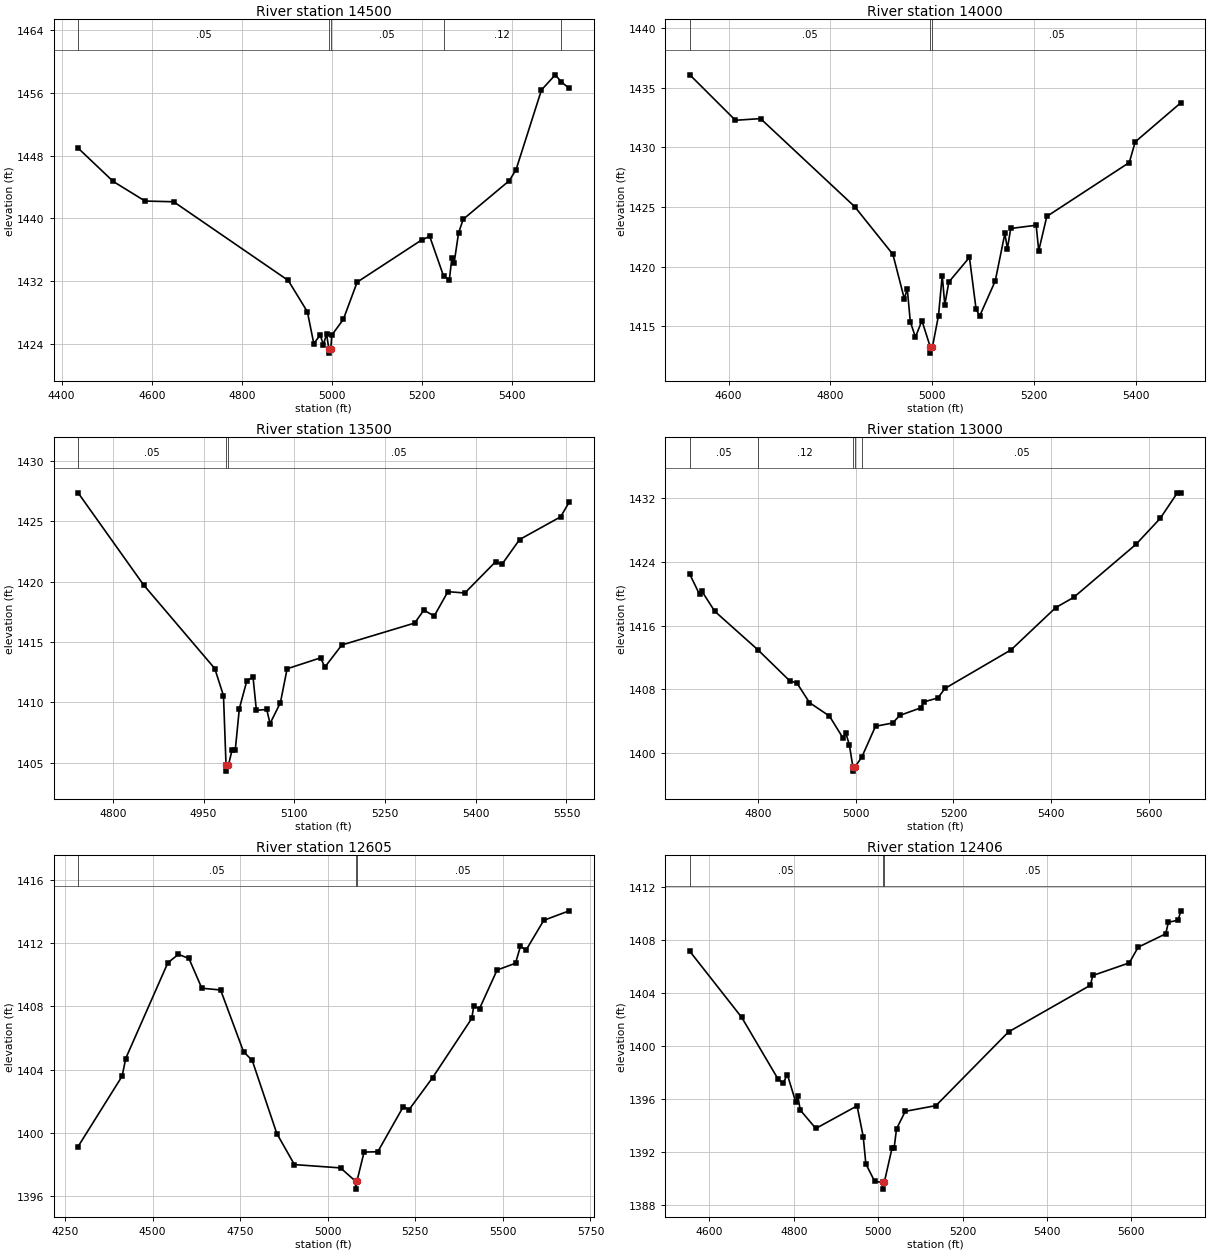
Type RM Length L Ch R = 1 ,14500   ,500,500,500
BEGIN DESCRIPTION:
SANFERNANDO049 29.0
END DESCRIPTION:
XS GIS Cut Line= 3
      2820355.66     10291153.09      2819970.66     10290741.62
      2819455.69     10290853.11
#Sta/Elev= 30
  4436.5 1448.96  4514.4 1444.72  4585.2 1442.22  4648.7 1442.13  4903.2 1432.11
  4945.7 1428.12  4959.9 1424.07    4974 1425.15  4981.4 1423.94  4988.2  1425.3
  4993.5 1423.36  4993.8 1422.86  4997.5 1423.36    5000 1425.16  5025.5 1427.16
  5056.2  1431.9  5199.5 1437.27  5217.3 1437.72  5248.2 1432.65  5260.9 1432.19
  5266.5 1434.98  5271.6 1434.36  5281.3 1438.14  5291.6  1439.9  5393.9 1444.81
    5409 1446.21  5465.5 1456.37  5496.2 1458.29  5508.9 1457.42  5526.9 1456.57
#Mann= 5 ,-1 , 0
  4436.5     .05       0  4993.5     .03       0  4997.5     .05       0
  5248.2     .12       0  5508.9     .05       0
Bank Sta=4993.5,4997.5
XS Rating Curve= 0 ,0
Exp/Cntr=0.3,0.1

Type RM Length L Ch R = 1 ,14000   ,500,500,500
BEGIN DESCRIPTION:
SANFERNANDO049 28.0
END DESCRIPTION:
XS GIS Cut Line= 3
      2820555.68     10290603.11      2820138.15     10290374.54
      2819655.71     10290453.11
#Sta/Elev= 30
    4524 1436.08  4613.6 1432.27  4662.9 1432.41  4847.9 1425.03    4923 1421.03
  4945.5  1417.3  4951.2 1418.16  4957.2 1415.38  4967.3 1414.09    4980 1415.47
  4996.6 1413.25  4996.8 1412.75  5000.6 1413.25  5012.6  1415.9  5019.9 1419.25
    5025  1416.8  5032.9 1418.71  5073.4 1420.78  5086.5 1416.41  5093.7 1415.88
  5124.1  1418.8    5143 1422.78    5148  1421.5  5154.5  1423.2  5204.5 1423.47
  5209.5 1421.33  5225.4 1424.21  5387.5 1428.73  5399.1 1430.46  5488.8 1433.74
#Mann= 3 ,-1 , 0
    4524     .05       0  4996.6     .03       0  5000.6     .05       0
Bank Sta=4996.6,5000.6
XS Rating Curve= 0 ,0
Exp/Cntr=0.3,0.1

Type RM Length L Ch R = 1 ,13500   ,500,500,500
BEGIN DESCRIPTION:
SANFERNANDO049 27.0
END DESCRIPTION:
XS GIS Cut Line= 3
      2820455.65     10289903.12      2820205.04     10289962.28
      2819705.68     10290203.11
#Sta/Elev= 30
  4742.5 1427.37  4850.8 1419.74  4968.5 1412.81  4982.9 1410.56  4987.1 1404.81
  4987.3 1404.31  4991.1 1404.81  4997.1 1406.07  5002.4 1406.07  5009.1 1409.49
  5021.5 1411.79  5031.7 1412.11  5037.3 1409.35  5054.4 1409.42  5059.9 1408.25
    5077 1409.98  5088.1 1412.79  5143.6  1413.7  5150.4 1412.92  5178.5 1414.76
    5299 1416.58  5314.2 1417.65  5331.3 1417.16  5353.9 1419.18    5382 1419.07
  5432.8 1421.66  5443.4 1421.45  5472.5  1423.5  5540.3 1425.38  5554.4 1426.59
#Mann= 3 ,-1 , 0
  4742.5     .05       0  4987.1     .05       0  4991.1     .05       0
Bank Sta=4987.1,4991.1
XS Rating Curve= 0 ,0
Exp/Cntr=0.3,0.1

Type RM Length L Ch R = 1 ,13000   ,395,395,395
BEGIN DESCRIPTION:
SANFERNANDO049 26.0
END DESCRIPTION:
XS GIS Cut Line= 3
       2820305.7     10289603.12      2819972.63     10289533.37
      2819455.68     10289953.12
#Sta/Elev= 30
  4659.7 1422.47  4679.6 1419.94  4684.7 1420.31  4710.8 1417.82    4799 1412.99
  4864.1  1409.1  4879.3 1408.79  4904.9 1406.34  4945.8 1404.65  4974.1 1401.84
  4979.2 1402.56  4986.7    1401  4993.9 1398.23  4994.1 1397.73  4997.9 1398.23
  5012.2 1399.51  5040.2 1403.37  5075.4 1403.78  5089.8 1404.73  5132.9 1405.68
  5139.3 1406.43  5168.1 1406.93  5182.4 1408.12  5318.1 1412.98  5409.4 1418.28
  5446.1 1419.56    5574 1426.24  5623.5 1429.49  5658.7 1432.71  5665.9 1432.66
#Mann= 5 ,-1 , 0
  4659.7     .05       0    4799     .12       0  4993.9     .07       0
  4997.9     .12       0  5012.2     .05       0
Bank Sta=4993.9,4997.9
XS Rating Curve= 0 ,0
Exp/Cntr=0.3,0.1

Type RM Length L Ch R = 1 ,12605   ,199,199,199
BEGIN DESCRIPTION:
Mapping XS d09e9f88
END DESCRIPTION:
XS GIS Cut Line= 4
      2820451.07     10289137.96      2819779.15     10289195.25
      2819352.06     10289408.79      2819129.37     10289522.73
#Sta/Elev= 30
  4287.1 1399.15  4412.9  1403.6    4423 1404.71  4543.4 1410.76  4573.5 1411.29
  4603.6 1411.03  4640.4 1409.15    4694 1409.04  4759.5 1405.14  4784.3 1404.59
  4854.5 1399.97  4904.7 1398.01  5036.5  1397.8  5079.2 1396.96  5079.4 1396.46
  5083.2 1396.96  5103.6  1398.8  5142.7 1398.82  5215.4 1401.66  5232.1 1401.48
  5299.2  1403.5    5411 1407.24  5416.6    1408  5433.4 1407.87  5483.4  1410.3
    5536 1410.73    5550 1411.79  5566.6 1411.58  5616.7 1413.44  5689.1 1414.04
#Mann= 3 ,-1 , 0
  4287.1     .05       0  5079.2     .03       0  5083.2     .05       0
Bank Sta=5079.2,5083.2
XS Rating Curve= 0 ,0
Exp/Cntr=0.3,0.1

Type RM Length L Ch R = 1 ,12406   ,406,406,406
BEGIN DESCRIPTION:
Mapping XS 6db11565
END DESCRIPTION:
XS GIS Cut Line= 4
      2820070.85     10289085.88      2819779.15     10289018.17
      2819445.81     10289111.92      2819020.17     10289407.79
#Sta/Elev= 30
  4553.4 1407.12  4676.5 1402.14  4761.8 1397.54  4774.3 1397.17  4784.6 1397.84
  4804.4 1395.78  4809.5 1396.19  4815.3 1395.16  4852.1 1393.78  4949.9 1395.48
  4964.5 1393.16  4970.7 1391.11  4991.5  1389.8  5010.3 1389.71  5010.5 1389.21
  5014.3 1389.71  5032.6 1392.27  5037.8 1392.31  5043.4 1393.75  5064.2 1395.07
  5136.9  1395.5  5308.9 1401.05  5502.7 1404.56  5508.8  1405.3  5595.3 1406.25
  5616.2 1407.43  5681.7 1408.44  5687.8 1409.31  5710.8 1409.46  5717.5 1410.17
#Mann= 3 ,-1 , 0
  4553.4     .05       0  5010.3     .03       0  5014.3     .05       0
Bank Sta=5010.3,5014.3
XS Rating Curve= 0 ,0
Exp/Cntr=0.3,0.1

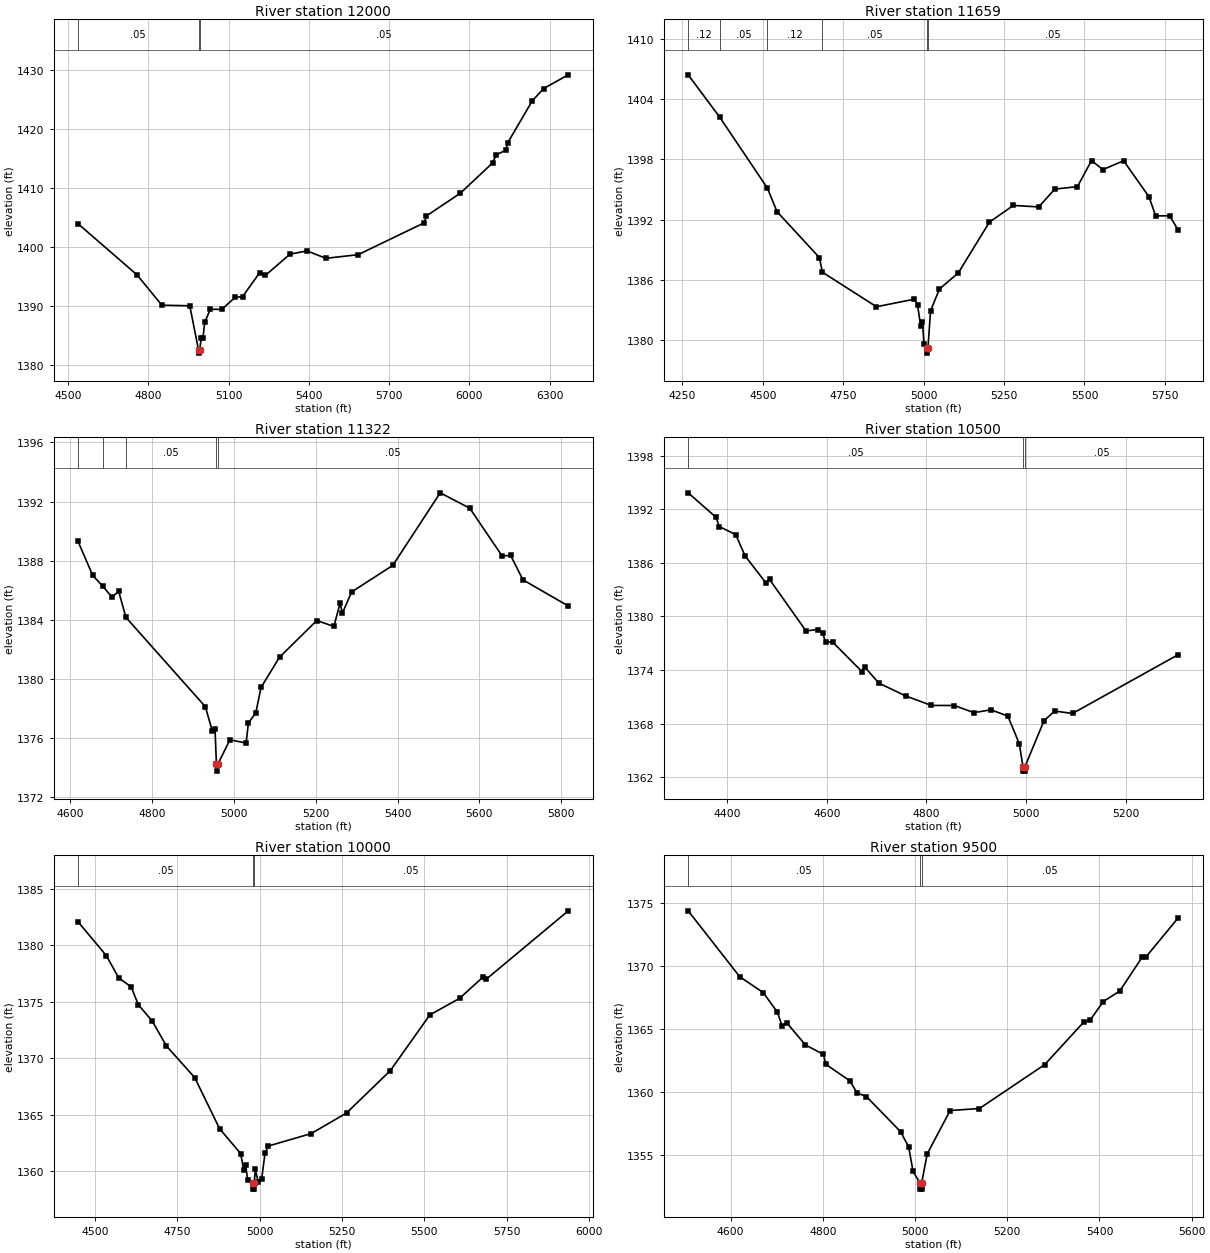
Type RM Length L Ch R = 1 ,12000   ,341,341,341
BEGIN DESCRIPTION:
SANFERNANDO049 24.0
END DESCRIPTION:
XS GIS Cut Line= 3
      2820005.65     10288953.09      2819607.07     10288718.89
      2818605.68     10289653.11
#Sta/Elev= 30
  4537.7 1403.94    4758 1395.25  4850.8 1390.09  4955.2 1389.99    4988 1382.44
  4988.3 1381.94    4992 1382.44  4997.9  1384.5  5004.4  1384.5  5011.1 1387.21
  5032.1  1389.4  5074.6 1389.37  5124.5 1391.42  5152.3 1391.55  5216.3 1395.61
  5237.3 1395.14  5329.6 1398.77  5393.2 1399.32    5464 1398.06  5584.2 1398.68
  5831.9 1404.11  5838.7 1405.25  5966.2 1409.13  6086.4 1414.27  6100.6 1415.67
  6136.2 1416.44  6143.1  1417.7  6234.9 1424.83  6277.4 1426.93  6369.5 1429.26
#Mann= 3 ,-1 , 0
  4537.7     .05       0    4988     .05       0    4992     .05       0
Bank Sta=4988,4992
XS Rating Curve= 0 ,0
Exp/Cntr=0.3,0.1

Type RM Length L Ch R = 1 ,11659   ,337,337,337
BEGIN DESCRIPTION:
Mapping XS 1d511bcf
END DESCRIPTION:
XS GIS Cut Line= 4
      2820346.86     10288690.05      2819732.27     10288408.79
      2819445.81     10288460.88      2819107.25     10288903.62
#Sta/Elev= 30
  4267.7 1406.39  4365.6 1402.19  4514.3 1395.12  4543.9 1392.79  4675.6 1388.23
  4685.2 1386.77  4853.2 1383.34  4970.6 1384.09  4980.8 1383.53  4990.8  1381.4
  4995.9 1381.84  5001.1 1379.67  5009.3 1379.23  5009.5 1378.73  5013.3 1379.23
  5021.4 1382.94  5049.2 1385.11  5107.7  1386.7  5204.4 1391.75  5278.9 1393.41
  5357.8 1393.26  5407.7 1395.03  5478.3 1395.28  5521.9 1397.87  5557.3 1396.97
  5621.7 1397.85  5700.6 1394.27  5721.4 1392.37    5765 1392.38  5792.1 1390.92
#Mann= 6 ,-1 , 0
  4267.7     .12       0  4365.6     .05       0  4514.3     .12       0
  4685.2     .05       0  5009.3     .03       0  5013.3     .05       0
Bank Sta=5009.3,5013.3
XS Rating Curve= 0 ,0
Exp/Cntr=0.3,0.1

Type RM Length L Ch R = 1 ,11322   ,822,822,822
BEGIN DESCRIPTION:
Mapping XS 28938d6d
END DESCRIPTION:
XS GIS Cut Line= 3
      2820227.08     10288330.68      2819753.11     10288127.54
      2819185.43     10288507.73
#Sta/Elev= 30
  4618.7  1389.3  4654.5    1387  4679.8 1386.25  4701.6 1385.53  4718.1 1385.92
  4735.7 1384.16  4930.1 1378.11  4946.6  1376.5  4953.6 1376.63  4957.1 1374.25
  4957.3 1373.75  4961.1 1374.25  4990.1 1375.87  5029.8 1375.65  5035.2    1377
  5053.4  1377.7  5066.3 1379.42  5111.4 1381.46  5202.4 1383.94  5244.4 1383.55
  5259.4 1385.11  5265.4 1384.46  5287.7 1385.88  5388.5 1387.68  5504.4 1392.59
  5576.6 1391.55  5655.7 1388.32  5676.7 1388.35  5706.7  1386.7  5817.6 1384.93
#Mann= 5 ,-1 , 0
  4618.7     .05       0  4679.8     .12       0  4735.7     .05       0
  4957.1     .03       0  4961.1     .05       0
Bank Sta=4957.1,4961.1
XS Rating Curve= 0 ,0
Exp/Cntr=0.3,0.1

Type RM Length L Ch R = 1 ,10500   ,500,500,500
BEGIN DESCRIPTION:
SANFERNANDO049 21.0
END DESCRIPTION:
XS GIS Cut Line= 3
      2820605.67     10287603.11      2819952.74     10287418.97
       2819755.7     10287653.09
#Sta/Elev= 30
  4321.6 1393.83  4377.8 1391.08  4383.9 1390.06    4417 1389.16  4435.9 1386.78
  4477.4 1383.77    4485 1384.14  4558.2 1378.38  4581.3 1378.54  4591.7  1378.1
  4597.4 1377.18  4612.5 1377.09  4670.6 1373.83  4675.8 1374.36  4704.6 1372.54
    4758 1371.12  4809.9 1370.05  4856.2 1370.04  4895.4 1369.24  4929.4 1369.56
  4963.5 1368.86  4986.5 1365.76  4993.9  1363.2  4994.1  1362.7  4997.6  1362.7
  4997.9  1363.2  5036.2 1368.35  5057.7 1369.42  5093.4 1369.15    5306 1375.74
#Mann= 3 ,-1 , 0
  4321.6     .05       0  4993.9     .05       0  4997.9     .05       0
Bank Sta=4993.9,4997.9
XS Rating Curve= 0 ,0
Exp/Cntr=0.3,0.1

Type RM Length L Ch R = 1 ,10000   ,500,500,500
BEGIN DESCRIPTION:
SANFERNANDO049 20.0
END DESCRIPTION:
XS GIS Cut Line= 3
      2819405.69     10286603.11      2819606.82     10287116.84
      2819655.68     10288053.07
#Sta/Elev= 30
  4448.3 1382.07  4534.2 1379.08  4571.8 1377.11  4609.4 1376.33  4631.4 1374.74
  4673.8 1373.29  4716.8 1371.09  4802.7  1368.3  4878.3 1363.78  4942.3 1361.58
  4951.7  1360.1  4957.1 1360.59  4963.8 1359.22  4979.5 1358.94  4979.8 1358.44
  4983.3 1358.44  4983.5 1358.94  4986.9 1360.18  4995.3  1359.1  5006.3 1359.37
  5016.3 1361.63  5026.3 1362.25  5156.5 1363.35  5263.8 1365.17  5396.8 1368.91
    5517 1373.84  5607.1  1375.3  5677.2 1377.15  5687.2 1376.97  5937.5 1383.04
#Mann= 3 ,-1 , 0
  4448.3     .05       0  4979.5     .05       0  4983.5     .05       0
Bank Sta=4979.5,4983.5
XS Rating Curve= 0 ,0
Exp/Cntr=0.3,0.1

Type RM Length L Ch R = 1 ,9500    ,500,500,500
BEGIN DESCRIPTION:
SANFERNANDO049 19.0
END DESCRIPTION:
XS GIS Cut Line= 3
      2819305.68     10286803.14      2819214.48     10287286.81
      2819605.71     10287703.14
#Sta/Elev= 30
  4507.8 1374.41  4619.7 1369.16  4670.6  1367.9  4701.4 1366.34  4711.3 1365.26
  4721.5  1365.5  4762.2 1363.73  4801.2 1362.98  4806.3 1362.19  4858.7 1360.87
  4874.1 1359.91  4894.5 1359.62  4968.7 1356.82  4986.1 1355.61  4995.6 1353.67
  5010.3 1352.75  5010.5 1352.25    5014 1352.25  5014.3 1352.75  5026.4 1355.06
  5076.2 1358.51  5139.7 1358.67  5281.4 1362.17  5365.9 1365.55  5380.1 1365.72
  5408.4 1367.19    5444 1368.02  5493.4 1370.76  5500.7 1370.73  5571.3 1373.87
#Mann= 3 ,-1 , 0
  4507.8     .05       0  5010.3     .05       0  5014.3     .05       0
Bank Sta=5010.3,5014.3
XS Rating Curve= 0 ,0
Exp/Cntr=0.3,0.1

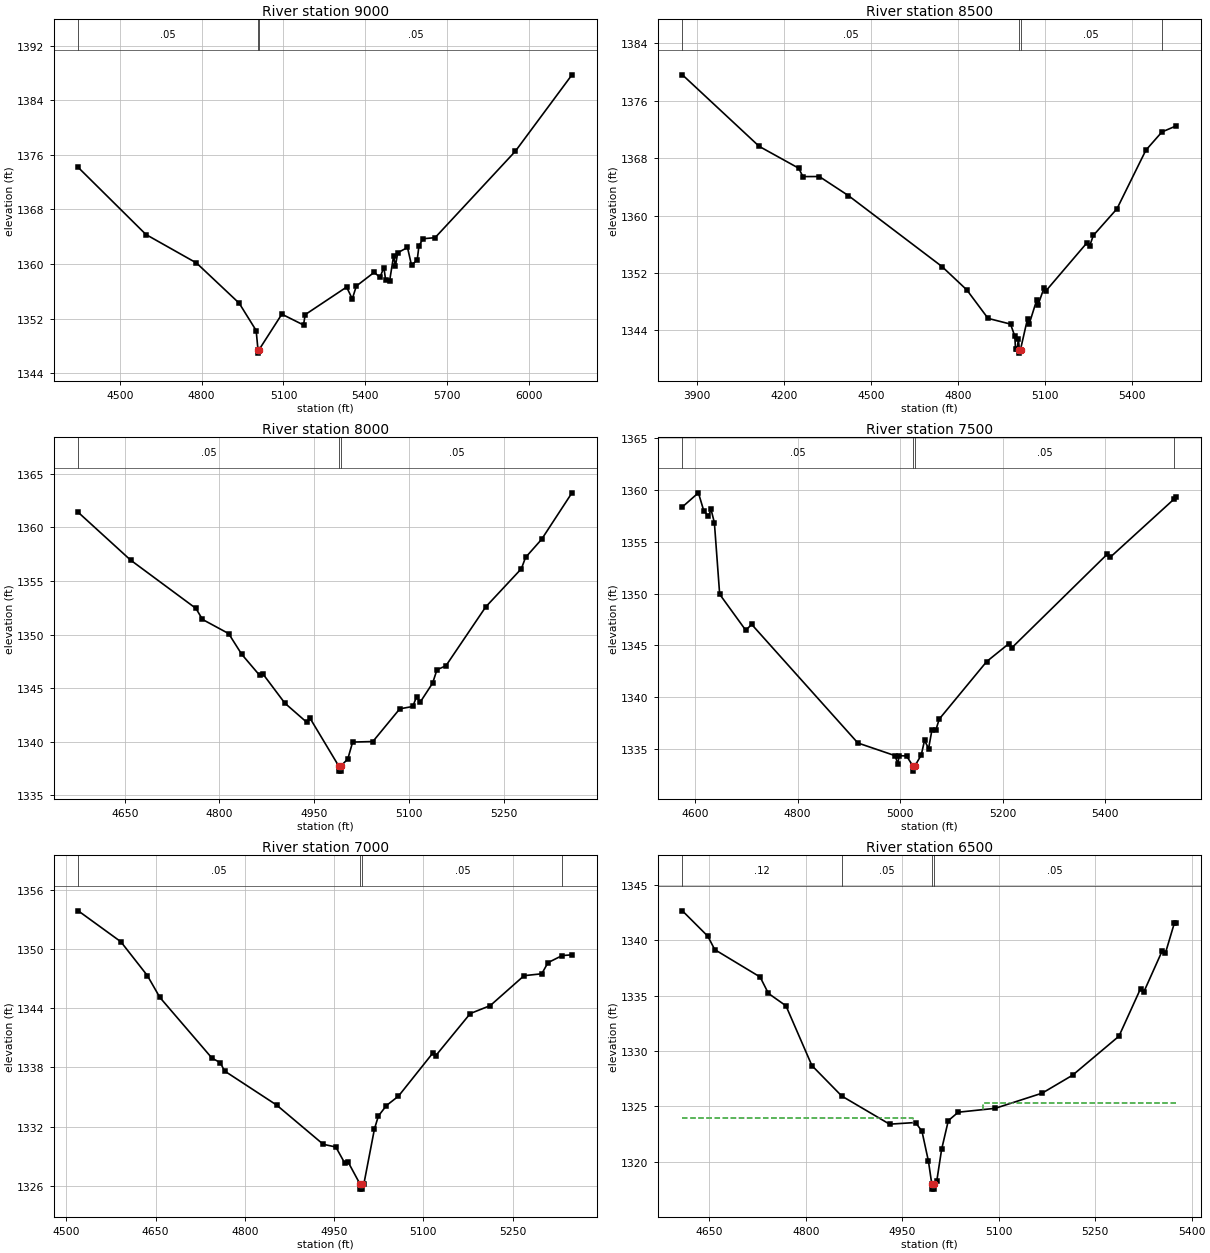
Type RM Length L Ch R = 1 ,9000    ,500,500,500
BEGIN DESCRIPTION:
SANFERNANDO049 18.0
END DESCRIPTION:
XS GIS Cut Line= 3
      2819155.68     10286753.12      2818740.97     10287256.11
      2819405.68     10288203.11
#Sta/Elev= 30
  4348.1 1374.14  4596.3 1364.31  4781.3 1360.14  4937.7 1354.25    5000 1350.24
  5006.6 1347.43  5006.8 1346.93  5010.6 1347.43  5094.1 1352.64  5173.5 1351.05
  5179.6 1352.57  5331.3 1356.61  5352.2 1354.88    5367 1356.76  5432.4 1358.77
  5453.3 1358.04  5468.1 1359.47  5474.2 1357.64    5489 1357.54  5503.8 1361.23
  5509.9 1359.63  5518.6 1361.64  5554.4 1362.41  5569.2  1359.8  5590.1 1360.59
  5596.2 1362.61    5611 1363.69  5655.5 1363.85  5949.3  1376.5    6157 1387.71
#Mann= 3 ,-1 , 0
  4348.1     .05       0  5006.6     .05       0  5010.6     .05       0
Bank Sta=5006.6,5010.6
XS Rating Curve= 0 ,0
Exp/Cntr=0.3,0.1

Type RM Length L Ch R = 1 ,8500    ,500,500,500
BEGIN DESCRIPTION:
SANFERNANDO049 17.0
END DESCRIPTION:
XS GIS Cut Line= 3
      2819255.71     10286653.09      2818327.73     10287330.97
       2817805.7     10287153.12
#Sta/Elev= 30
  3850.8 1379.59  4115.3 1369.63  4251.3 1366.59  4265.9 1365.42  4322.3 1365.43
  4422.7 1362.77  4744.8  1352.9  4830.5 1349.64  4903.5 1345.68  4981.1 1344.88
  4995.7  1343.2  4998.2 1341.44  5003.7 1341.44  5008.2 1342.81  5011.4 1341.34
  5011.7 1340.84  5015.4 1341.34  5039.5 1345.62  5044.8 1344.83  5070.9  1348.2
  5076.1 1347.59  5096.9 1349.97  5102.2 1349.47  5245.1 1356.24  5253.7 1355.78
  5266.3 1357.23  5347.7 1360.94  5447.1 1369.09  5502.4 1371.63  5551.5 1372.48
#Mann= 4 ,-1 , 0
  3850.8     .05       0  5011.4     .05       0  5015.4     .05       0
  5502.4     .12       0
Bank Sta=5011.4,5015.4
XS Rating Curve= 0 ,0
Exp/Cntr=0.3,0.1

Type RM Length L Ch R = 1 ,8000    ,500,500,500
BEGIN DESCRIPTION:
SANFERNANDO049 16.0
END DESCRIPTION:
XS GIS Cut Line= 3
      2818755.64      10286953.1       2818346.5     10286843.38
      2818005.73      10286953.1
#Sta/Elev= 30
  4576.4  1361.4  4659.2 1356.95  4762.7 1352.44  4773.1 1351.41  4814.5 1350.09
  4835.2 1348.16  4863.5  1346.2  4868.7 1346.33  4903.5  1343.6  4938.3 1341.81
  4943.5 1342.18  4988.5 1337.76  4988.7 1337.26  4992.2 1337.26  4992.5 1337.76
  5003.1 1338.39  5010.8 1339.97  5042.8 1340.02  5085.4 1343.07  5105.9 1343.29
  5112.2 1344.22  5117.5 1343.67  5137.4 1345.47  5144.3 1346.72  5158.4 1347.08
  5221.5 1352.58  5277.9 1356.14  5284.5 1357.19  5309.9 1358.88    5358 1363.22
#Mann= 3 ,-1 , 0
  4576.4     .05       0  4988.5     .05       0  4992.5     .05       0
Bank Sta=4988.5,4992.5
XS Rating Curve= 0 ,0
Exp/Cntr=0.3,0.1

Type RM Length L Ch R = 1 ,7500    ,500,500,500
BEGIN DESCRIPTION:
SANFERNANDO049 15.0
END DESCRIPTION:
XS GIS Cut Line= 3
      2818605.65      10286503.1      2818197.11     10286386.68
      2817855.69     10286803.11
#Sta/Elev= 30
  4575.2 1358.37  4606.4 1359.73  4616.8 1358.01  4625.9 1357.47  4631.1 1358.12
  4637.6 1356.84  4647.9 1349.93  4698.8 1346.45  4710.3 1347.02  4917.5 1335.56
  4990.3 1334.33  4995.5 1333.52  4998.1 1334.33  5012.5 1334.31  5024.8 1333.34
  5025.1 1332.84  5028.8 1333.34  5041.2  1334.4  5047.6 1335.81  5055.5 1335.02
    5062  1336.8  5069.9 1336.85  5076.3 1337.87  5168.9 1343.43    5212 1345.15
  5218.4 1344.78  5403.6 1353.78    5410 1353.51  5534.3 1359.12  5538.5 1359.28
#Mann= 4 ,-1 , 0
  4575.2     .05       0  5024.8     .05       0  5028.8     .05       0
  5534.3     .12       0
Bank Sta=5024.8,5028.8
XS Rating Curve= 0 ,0
Exp/Cntr=0.3,0.1

Type RM Length L Ch R = 1 ,7000    ,500,500,500
BEGIN DESCRIPTION:
SANFERNANDO049 14.0
END DESCRIPTION:
XS GIS Cut Line= 3
      2818505.68     10286203.11       2818103.5     10285940.92
      2817755.65     10285903.11
#Sta/Elev= 30
  4519.9 1353.87  4591.5 1350.74  4636.1 1347.31  4657.2 1345.09  4744.8 1338.94
  4758.6 1338.49  4765.9 1337.64  4853.4 1334.19  4931.8 1330.21  4952.9 1329.94
    4968  1328.3    4974 1328.37  4993.7 1326.17    4994 1325.67  4997.5 1325.67
  4997.7 1326.17    5000 1326.17  5017.9 1331.78  5024.5 1333.08    5038 1334.14
  5058.2 1335.09    5116 1339.46    5121  1339.2  5178.9 1343.46  5212.6 1344.27
  5269.4  1347.3  5299.1 1347.49  5309.6 1348.62  5333.5 1349.34  5349.9 1349.41
#Mann= 4 ,-1 , 0
  4519.9     .05       0  4993.7     .05       0  4997.7     .05       0
  5333.5     .12       0
Bank Sta=4993.7,4997.7
XS Rating Curve= 0 ,0
Exp/Cntr=0.3,0.1

Type RM Length L Ch R = 1 ,6500    ,500,500,500
BEGIN DESCRIPTION:
SANFERNANDO049 13.0
END DESCRIPTION:
XS GIS Cut Line= 3
      2818455.67     10285403.11      2818066.53     10285447.76
      2817705.69     10285553.11
#Sta/Elev= 30
  4608.3 1342.65  4647.8 1340.36  4658.6 1339.15  4729.1 1336.68    4742  1335.2
  4769.3 1334.08  4809.6 1328.69    4856 1325.94  4930.4  1323.4  4970.7 1323.55
  4980.7 1322.77  4990.8 1320.06  4995.9 1318.04  4996.2 1317.54  4999.7 1317.54
  4999.9 1318.04  5003.7 1318.25  5011.3 1321.13  5021.7 1323.72  5037.1 1324.48
  5094.6 1324.83  5167.6  1326.2  5214.9 1327.82    5287 1331.34  5320.5 1335.62
  5325.7 1335.34    5354 1339.01  5359.2 1338.83  5373.3 1341.58  5375.9 1341.58
#Mann= 4 ,-1 , 0
  4608.3     .12       0    4856     .05       0  4995.9     .05       0
  4999.9     .05       0
#XS Ineff= 2 , 0
         4966.14 1323.94 5075.24         1325.29
Permanent Ineff=
       F       F
Bank Sta=4995.9,4999.9
XS Rating Curve= 0 ,0
Exp/Cntr=0.3,0.1

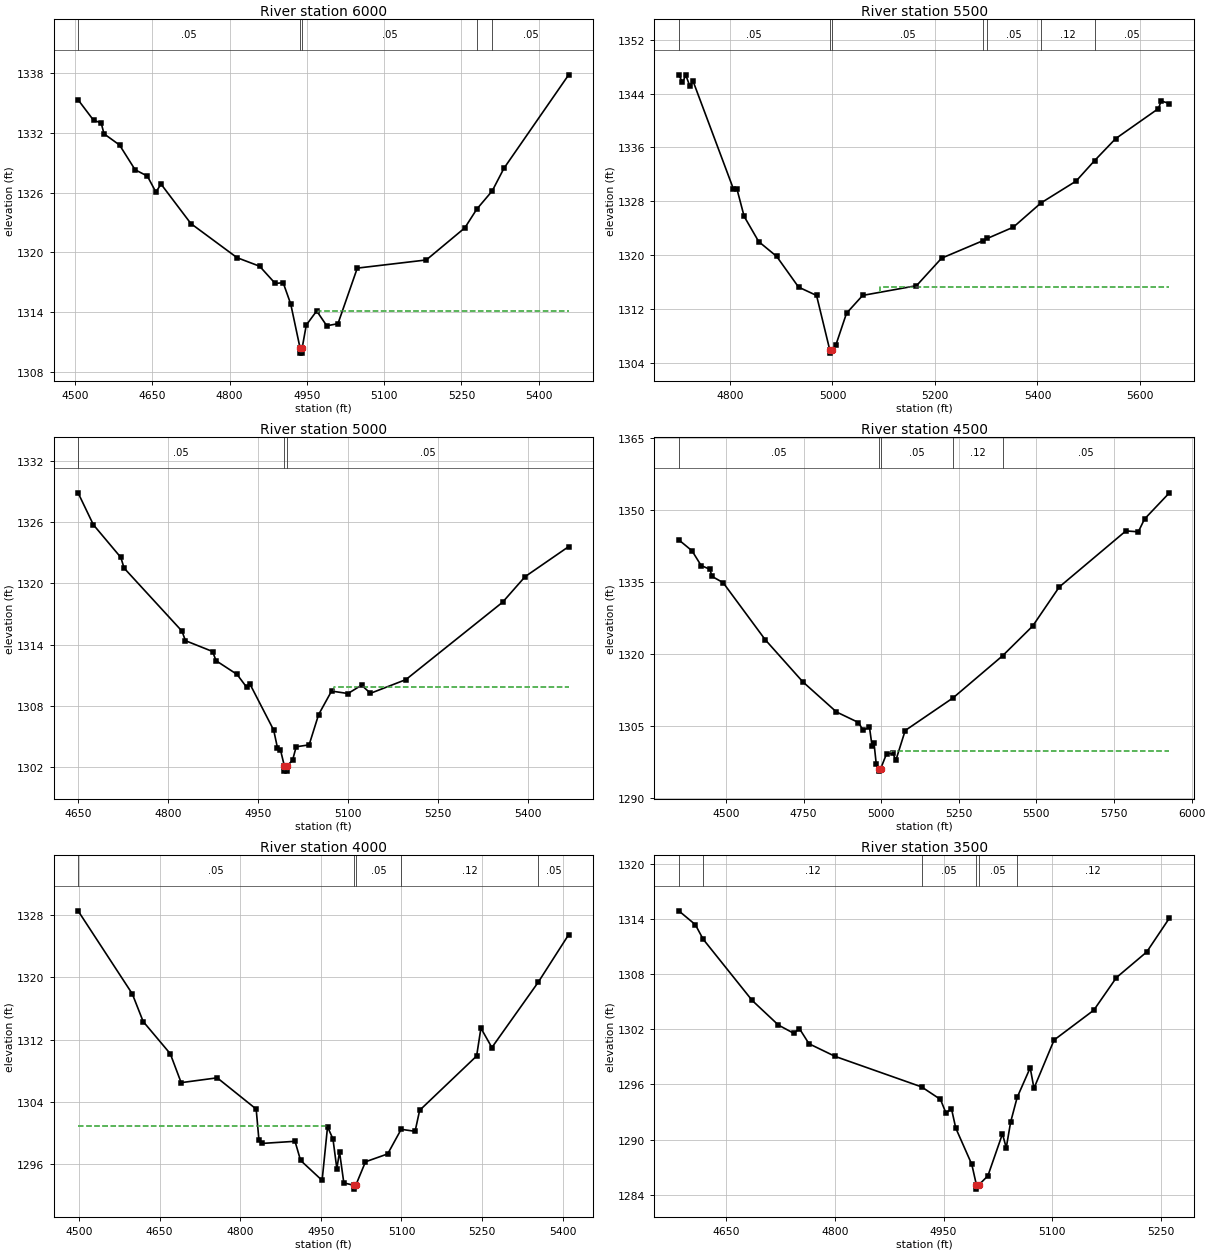
Type RM Length L Ch R = 1 ,6000    ,500,500,500
BEGIN DESCRIPTION:
SANFERNANDO049 12.0
END DESCRIPTION:
XS GIS Cut Line= 3
      2817805.68     10284553.09      2817861.45     10285043.84
      2817655.68     10285453.12
#Sta/Elev= 30
  4506.1 1335.33  4536.3 1333.26  4550.9 1333.01  4556.4 1331.91  4586.6 1330.78
  4616.8 1328.29  4640.5 1327.66  4657.1 1326.05  4667.1 1326.85    4725 1322.88
  4814.6 1319.45  4858.4 1318.59  4888.6 1316.86  4904.1 1316.93  4918.8 1314.78
  4936.9 1310.35  4937.1 1309.85  4940.6 1309.85  4940.9 1310.35  4948.9 1312.67
  4969.1 1314.09  4988.7  1312.6  5010.4 1312.81  5047.9  1318.4  5181.8 1319.22
  5256.6 1322.45  5279.9 1324.34  5309.7 1326.16  5332.5 1328.44  5458.1 1337.84
#Mann= 5 ,-1 , 0
  4506.1     .05       0  4936.9     .05       0  4940.9     .05       0
  5279.9     .12       0  5309.7     .05       0
#XS Ineff= 2 , 0
                         4971.79          1314.1
Permanent Ineff=
       F       F
Bank Sta=4936.9,4940.9
XS Rating Curve= 0 ,0
Exp/Cntr=0.3,0.1

Type RM Length L Ch R = 1 ,5500    ,500,500,500
BEGIN DESCRIPTION:
SANFERNANDO049 11.0
END DESCRIPTION:
XS GIS Cut Line= 3
       2817255.7     10284703.13       2817455.2     10284927.05
      2817655.69     10285553.13
#Sta/Elev= 30
  4700.1 1346.77  4707.2 1345.67  4713.9  1346.7  4721.4 1345.14  4728.1  1345.8
  4806.7 1329.84  4813.4 1329.89  4827.6 1325.78    4856 1322.04  4891.1 1319.84
  4933.8 1315.29  4968.9 1314.05  4994.6    1306  4994.9  1305.5  4998.6    1306
  5006.4 1306.66  5027.4 1311.42  5058.9 1314.06  5163.9  1315.5  5212.9 1319.58
  5294.1 1322.19  5302.2 1322.51  5352.9 1324.18  5406.8 1327.77  5475.3 1331.01
  5511.3 1334.04  5552.4  1337.3  5636.1 1341.77  5641.3  1342.9  5657.4 1342.51
#Mann= 7 ,-1 , 0
  4700.1     .05       0  4994.6     .05       0  4998.6     .05       0
  5294.1     .12       0  5302.2     .05       0  5406.8     .12       0
  5511.3     .05       0
#XS Ineff= 2 , 0
                         5092.79         1315.34
Permanent Ineff=
       F       F
Bank Sta=4994.6,4998.6
XS Rating Curve= 0 ,0
Exp/Cntr=0.3,0.1

Type RM Length L Ch R = 1 ,5000    ,500,500,500
BEGIN DESCRIPTION:
SANFERNANDO049 10.0
END DESCRIPTION:
XS GIS Cut Line= 3
      2816955.69     10284803.14      2817023.98     10285146.82
      2817255.68      10285553.1
#Sta/Elev= 30
  4649.6 1328.84  4675.1 1325.72  4720.9 1322.52  4726.3 1321.48  4822.9 1315.31
  4828.6 1314.38  4873.9 1313.32  4879.7 1312.42  4914.7 1311.08  4930.9 1309.81
    4936 1310.16  4975.8 1305.63    4982 1303.92  4987.1  1303.7  4993.6 1302.12
  4993.8 1301.62  4997.3 1301.62  4997.6 1302.12  5007.2 1302.67  5013.3    1304
  5034.9 1304.19  5050.7 1307.15  5072.3 1309.45  5099.7 1309.21  5122.4 1310.03
  5137.1 1309.23  5196.2 1310.57  5357.5 1318.14    5395 1320.64  5467.7 1323.58
#Mann= 3 ,-1 , 0
  4649.6     .05       0  4993.6     .05       0  4997.6     .05       0
#XS Ineff= 2 , 0
                         5076.49         1309.86
Permanent Ineff=
       F       F
Bank Sta=4993.6,4997.6
XS Rating Curve= 0 ,0
Exp/Cntr=0.3,0.1

Type RM Length L Ch R = 1 ,4500    ,500,500,500
BEGIN DESCRIPTION:
SANFERNANDO049 9.0
END DESCRIPTION:
XS GIS Cut Line= 3
      2816955.67     10284653.13      2816566.36     10285175.63
      2816605.68      10286103.1
#Sta/Elev= 30
  4348.4 1343.79  4391.1  1341.5  4420.3 1338.43  4448.1 1337.66  4455.8 1336.15
  4491.2 1334.85  4626.8 1322.94  4747.7 1314.16  4856.2 1307.86    4927 1305.66
  4941.6 1304.07  4962.5 1304.65  4970.8 1300.75  4977.1 1301.34  4984.4  1296.9
  4994.4 1296.01  4994.6 1295.51  4998.4 1296.01  5017.5 1299.13  5037.5 1299.24
  5047.5  1297.8  5077.5 1303.99  5231.8 1310.81  5391.1 1319.59  5487.9 1325.79
  5573.6 1333.95  5788.2 1345.66  5828.2 1345.47  5848.2 1348.14  5928.3 1353.61
#Mann= 5 ,-1 , 0
  4348.4     .05       0  4994.4     .05       0  4998.4     .05       0
  5231.8     .12       0  5391.1     .05       0
#XS Ineff= 2 , 0
                         5032.29         1299.73
Permanent Ineff=
       F       F
Bank Sta=4994.4,4998.4
XS Rating Curve= 0 ,0
Exp/Cntr=0.3,0.1

Type RM Length L Ch R = 1 ,4000    ,500,500,500
BEGIN DESCRIPTION:
SANFERNANDO049 8.0
END DESCRIPTION:
XS GIS Cut Line= 3
      2816005.68      10284703.1      2816073.12     10285200.34
      2816155.68     10285603.07
#Sta/Elev= 30
  4498.2 1328.53  4599.1 1317.87  4619.3 1314.32  4669.8 1310.18    4690 1306.47
  4757.1 1307.09  4829.6 1303.08  4834.7 1299.15  4841.3 1298.67  4901.9 1298.94
  4912.2 1296.49  4952.3 1293.92  4962.4  1300.8  4972.5 1299.24  4979.7 1295.43
  4984.7 1297.58  4992.7  1293.6    5011  1293.3  5011.3  1292.8    5015  1293.3
    5033 1296.31  5074.3 1297.32  5099.4 1300.48  5125.3 1300.22  5133.8 1302.92
  5239.8 1309.89  5247.8 1313.47  5268.2 1310.98  5354.4 1319.36  5411.1 1325.47
#Mann= 5 ,-1 , 0
  4498.2     .05       0    5011     .05       0    5015     .05       0
  5099.4     .12       0  5354.4     .05       0
#XS Ineff= 2 , 0
         4962.38  1300.9
Permanent Ineff=
       F       F
Bank Sta=5011,5015
XS Rating Curve= 0 ,0
Exp/Cntr=0.3,0.1

Type RM Length L Ch R = 1 ,3500    ,500,500,500
BEGIN DESCRIPTION:
SANFERNANDO049 7.0
END DESCRIPTION:
XS GIS Cut Line= 3
      2815905.68     10284953.12      2815680.41     10285302.25
      2815755.68      10285553.1
#Sta/Elev= 30
  4584.5 1314.86  4607.3 1313.36  4618.1 1311.78  4685.8 1305.12  4722.1 1302.44
  4743.2 1301.55  4751.1 1302.05  4764.3 1300.41  4800.6 1299.03  4919.8 1295.72
  4945.8 1294.36  4953.4 1292.88    4961 1293.35  4966.9 1291.25  4989.1 1287.29
  4995.3 1285.11  4995.5 1284.61  4999.3 1285.11  5011.3 1286.06  5031.4 1290.62
  5036.6  1289.1  5042.7  1291.9  5051.7 1294.58  5069.7  1297.8  5074.9 1295.57
  5102.7 1300.82  5157.5 1304.06  5188.8 1307.61  5230.6 1310.39  5261.9 1314.07
#Mann= 6 ,-1 , 0
  4584.5     .05       0  4618.1     .12       0  4919.8     .05       0
  4995.3     .05       0  4999.3     .05       0  5051.7     .12       0
Bank Sta=4995.3,4999.3
XS Rating Curve= 0 ,0
Exp/Cntr=0.3,0.1

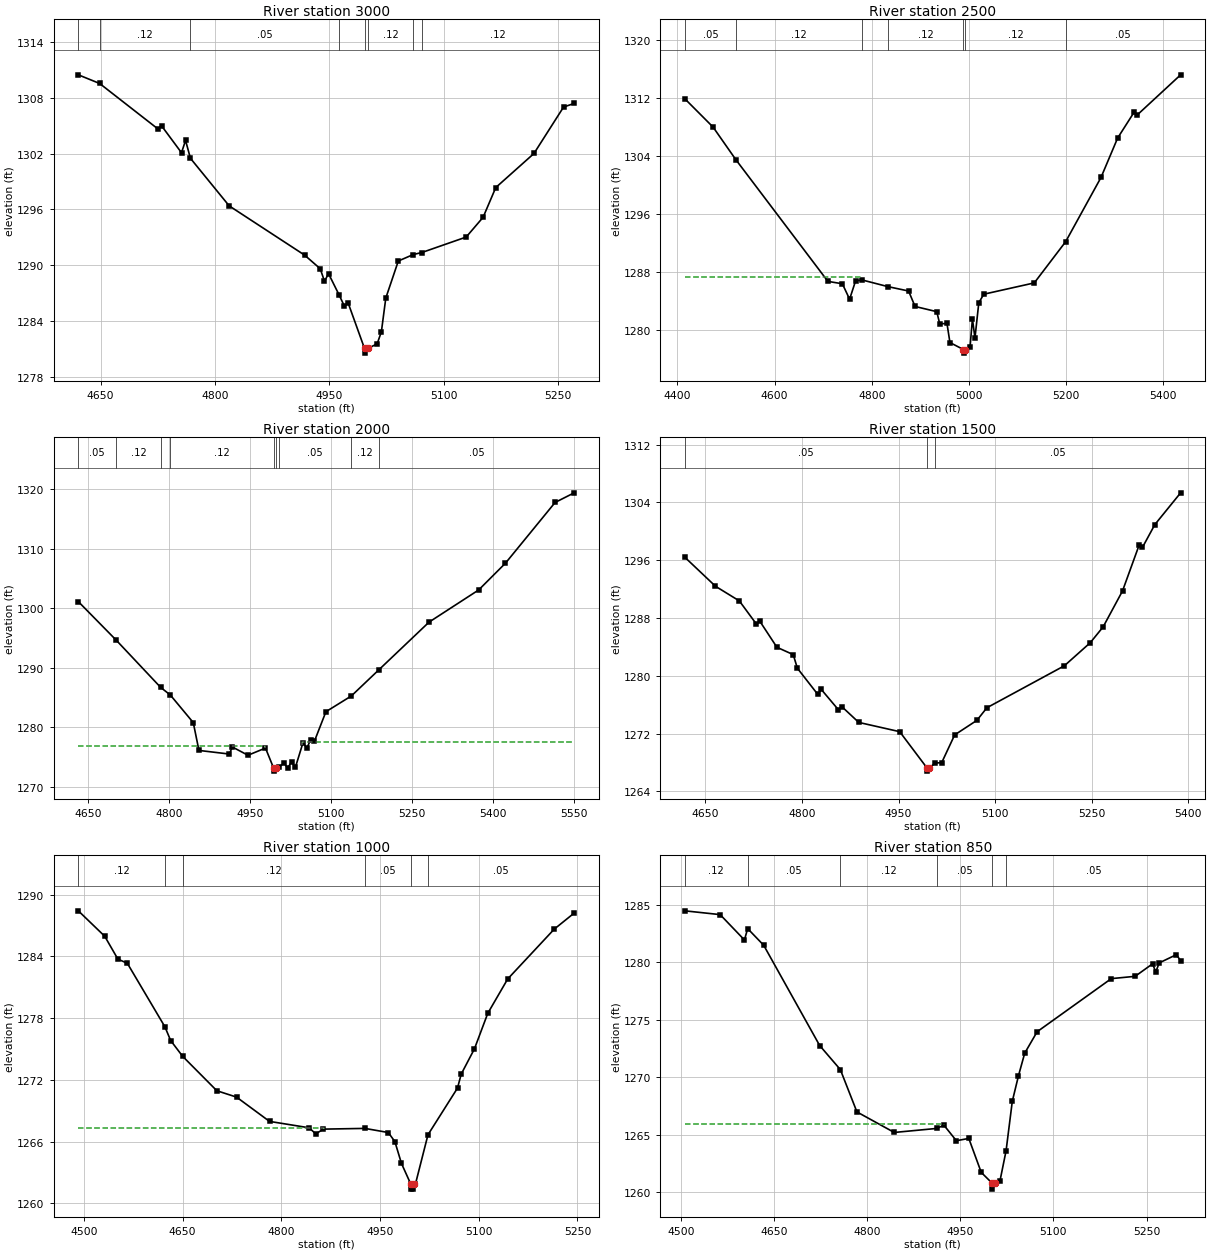
Type RM Length L Ch R = 1 ,3000    ,500,500,500
BEGIN DESCRIPTION:
SANFERNANDO049 6.0
END DESCRIPTION:
XS GIS Cut Line= 3
      2815355.69      10284903.1      2815232.45     10285261.61
      2815355.67     10285503.09
#Sta/Elev= 30
  4620.9  1310.5  4648.8 1309.57    4725 1304.69  4730.3 1304.98  4756.2 1302.11
  4761.5 1303.44  4767.9 1301.51  4818.7 1296.39  4917.7 1291.08  4938.1 1289.62
  4943.7 1288.27    4949 1289.09  4963.2 1286.74  4969.6 1285.62  4974.9 1285.89
  4996.2 1281.03  4996.4 1280.53  5000.2 1281.03  5012.7 1281.52  5018.3 1282.83
  5024.1 1286.46  5040.5 1290.45  5060.2 1291.15  5071.2 1291.36  5129.5 1293.03
  5151.7 1295.16  5168.3 1298.36  5218.4 1302.03  5257.2 1307.03  5271.1 1307.42
#Mann= 8 ,-1 , 0
  4620.9     .05       0  4648.8     .12       0  4767.9     .05       0
  4963.2     .12       0  4996.2     .07       0  5000.2     .12       0
  5060.2     .05       0  5071.2     .12       0
Bank Sta=4996.2,5000.2
XS Rating Curve= 0 ,0
Exp/Cntr=0.3,0.1

Type RM Length L Ch R = 1 ,2500    ,500,500,500
BEGIN DESCRIPTION:
SANFERNANDO049 5.0
END DESCRIPTION:
XS GIS Cut Line= 3
      2814255.65     10284953.09      2814738.03     10285283.51
      2814855.69     10285703.12
#Sta/Elev= 30
  4415.3 1311.96  4473.6 1308.04  4520.4 1303.55  4709.8 1286.76  4739.6 1286.43
  4754.5  1284.3  4766.9 1286.85  4780.6 1286.95  4833.1 1286.04  4875.9 1285.43
  4889.2  1283.3  4933.9 1282.58    4940 1280.89  4954.9 1280.96    4961 1278.32
  4988.7 1277.36    4989 1276.86  4992.8 1277.36  5002.4 1277.69  5007.3 1281.57
  5012.5 1278.94  5020.4 1283.81  5030.7 1284.99  5134.6 1286.55  5199.2 1292.24
    5272 1301.11  5306.1 1306.53  5340.2 1310.12  5345.3 1309.65  5435.8 1315.26
#Mann= 7 ,-1 , 0
  4415.3     .05       0  4520.4     .12       0  4780.6     .05       0
  4833.1     .12       0  4988.7     .07       0  4992.8     .12       0
  5199.2     .05       0
#XS Ineff= 2 , 0
            4775 1287.32
Permanent Ineff=
       F       F
Bank Sta=4988.7,4992.8
XS Rating Curve= 0 ,0
Exp/Cntr=0.3,0.1

Type RM Length L Ch R = 1 ,2000    ,500,500,500
BEGIN DESCRIPTION:
SANFERNANDO049 4.0
END DESCRIPTION:
XS GIS Cut Line= 3
      2814255.68     10285103.08      2814314.59     10285466.24
      2814705.67      10285853.1
#Sta/Elev= 30
  4632.1 1301.12  4702.2 1294.64  4784.5  1286.7  4802.4 1285.42  4844.9 1280.78
  4855.4  1276.1  4911.9 1275.49    4917 1276.69  4946.2 1275.29  4978.6  1276.5
  4993.7 1273.12    4994 1272.62    4998 1273.12  5004.1  1273.3  5012.7    1274
  5019.8 1273.13  5026.9 1274.19  5033.9 1273.23    5048 1277.39  5055.2 1276.49
  5062.2 1277.89  5069.3 1277.67  5090.5 1282.61  5137.6 1285.26  5188.7 1289.67
  5281.4 1297.67  5373.3 1303.08  5422.9 1307.58  5514.8 1317.79  5550.1 1319.41
#Mann= 9 ,-1 , 0
  4632.1     .05       0  4702.2     .12       0  4784.5     .05       0
  4802.4     .12       0  4993.7     .07       0    4998     .12       0
  5004.1     .05       0  5137.6     .12       0  5188.7     .05       0
#XS Ineff= 2 , 0
         4977.84 1276.79 5046.59         1277.44
Permanent Ineff=
       F       F
Bank Sta=4993.7,4998
XS Rating Curve= 0 ,0
Exp/Cntr=0.3,0.1

Type RM Length L Ch R = 1 ,1500    ,500,500,500
BEGIN DESCRIPTION:
SANFERNANDO049 3.0
END DESCRIPTION:
XS GIS Cut Line= 3
       2813955.7     10285203.08      2813836.31     10285566.05
      2813805.68     10285953.14
#Sta/Elev= 30
  4617.9 1296.41  4665.6 1292.39  4702.7 1290.36  4729.2 1287.15  4734.5 1287.55
    4761 1283.95  4786.4 1282.93  4792.8 1281.05  4824.6 1277.42  4829.9 1278.12
  4856.4 1275.32  4861.7 1275.75  4888.2 1273.55  4951.8 1272.27  4993.7 1267.31
    4994 1266.81    4998 1267.31  5007.1 1267.92  5017.1 1267.99  5037.2 1271.82
  5071.8 1273.84  5087.3 1275.58  5207.7 1281.39  5247.8 1284.57  5267.9 1286.77
    5298 1291.74    5324 1298.13    5329 1297.77  5348.2 1300.92  5388.3 1305.32
#Mann= 3 ,-1 , 0
  4617.9     .05       0  4993.7     .07       0  5007.1     .05       0
Bank Sta=4993.7,4998
XS Rating Curve= 0 ,0
Exp/Cntr=0.3,0.1

Type RM Length L Ch R = 1 ,1000    ,150,150,150
BEGIN DESCRIPTION:
SANFERNANDO049 2.0
END DESCRIPTION:
XS GIS Cut Line= 3
      2813305.69     10285103.13      2813340.11     10285610.57
      2813305.68     10285853.14
#Sta/Elev= 30
  4491.4 1288.43  4531.5 1285.96  4551.5 1283.74  4565.9 1283.33    4623 1277.16
  4631.7 1275.83    4650 1274.29  4701.9 1270.95  4731.9 1270.33    4782 1267.97
  4842.2 1267.35  4852.2 1266.76    4864 1267.22    4927 1267.29  4962.5 1266.89
  4972.5 1266.01  4982.5 1263.89  4996.6 1261.89  4996.9 1261.39  5000.7 1261.39
  5000.9 1261.89  5003.8 1261.89  5022.8 1266.67  5067.7 1271.21  5073.3 1272.56
  5093.5 1275.03  5113.7 1278.47    5144 1281.81  5214.7 1286.65    5245 1288.21
#Mann= 6 ,-1 , 0
  4491.4     .12       0    4623     .05       0    4650     .12       0
    4927     .05       0  4996.6     .07       0  5022.8     .05       0
#XS Ineff= 2 , 0
         4864.77 1267.36
Permanent Ineff=
       F       F
Bank Sta=4996.6,5000.9
XS Rating Curve= 0 ,0
Exp/Cntr=0.3,0.1

Type RM Length L Ch R = 1 ,850     ,511,511,511
BEGIN DESCRIPTION:
Mapping XS 39625d48
END DESCRIPTION:
XS GIS Cut Line= 4
      2813206.09     10285036.28      2813223.45     10285413.86
      2813223.45     10285643.89       2813169.2     10285826.18
#Sta/Elev= 30
  4506.6  1284.5  4563.5 1284.17  4602.6 1281.96  4607.8 1282.95  4633.6  1281.5
  4723.7 1272.76    4757 1270.66  4783.7 1266.97  4843.8 1265.18    4912 1265.53
  4923.8 1265.81  4943.8 1264.46  4963.8 1264.66  4983.8  1261.7  5001.7 1260.74
  5001.9 1260.24    5006 1260.74  5013.8 1260.91  5023.8 1263.58  5033.8 1267.89
  5043.8 1270.13  5053.8 1272.09  5073.8 1273.96  5193.2 1278.59  5231.6 1278.79
  5259.6 1279.88  5264.8 1279.17  5270.3 1279.96    5298 1280.68  5304.8 1280.15
#Mann= 6 ,-1 , 0
  4506.6     .12       0  4607.8     .05       0    4757     .12       0
    4912     .05       0  5001.7     .07       0  5023.8     .05       0
#XS Ineff= 2 , 0
          4923.3 1265.89
Permanent Ineff=
       F       F
Bank Sta=5001.7,5006
XS Rating Curve= 0 ,0
Exp/Cntr=0.3,0.1