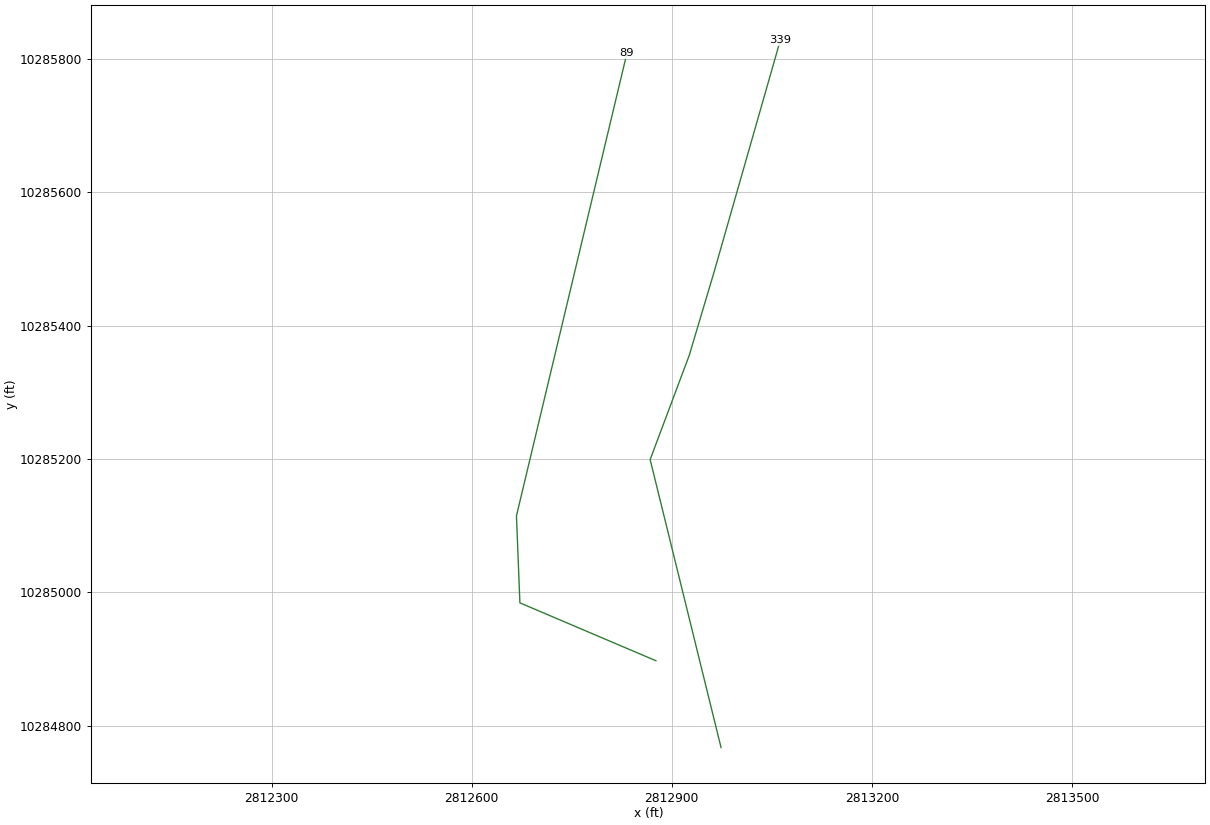
HEC-RAS study SANFERNANDO049.prj: SANFERNANDO049 Base Level Engineering

--- SANFERNANDO049.g01 (geometry) --- (continued)

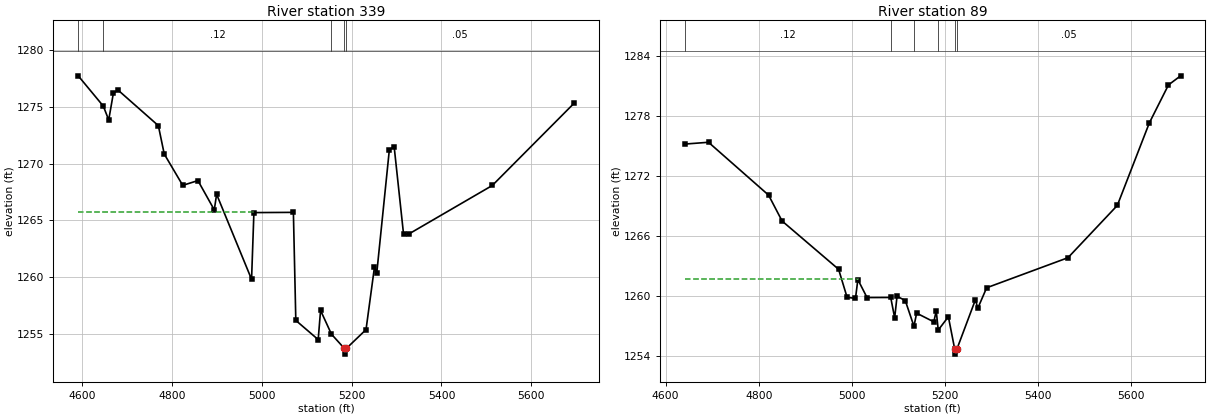
Type RM Length L Ch R = 1 ,339     ,250,250,250
BEGIN DESCRIPTION:
Mapping XS 15028625
END DESCRIPTION:
XS GIS Cut Line= 5
      2812973.88     10284767.15      2812867.54     10285199.01
      2812926.14     10285355.26      2812963.03     10285478.96
      2813062.83     10285828.27
#Sta/Elev= 30
  4591.3 1277.74  4647.2 1275.07  4659.2 1273.85  4669.5  1276.2  4679.8 1276.49
  4769.7 1273.35  4782.8 1270.85    4824 1268.09  4857.8 1268.51  4894.2 1265.93
  4899.4  1267.3  4977.2 1259.81  4982.4 1265.69  5070.3 1265.71  5075.7 1256.19
  5125.5  1254.5  5130.8 1257.07    5155 1254.98  5183.8 1253.72  5184.1 1253.22
  5188.2 1253.72    5232 1255.38  5250.7 1260.86    5256 1260.41  5283.9 1271.22
  5294.6  1271.5  5315.5  1263.8  5327.5 1263.81  5513.1 1268.08  5695.3 1275.33
#Mann= 5 ,-1 , 0
  4591.3     .05       0  4647.2     .12       0    5155     .05       0
  5183.8     .07       0  5188.2     .05       0
#XS Ineff= 2 , 0
         4983.07 1265.75
Permanent Ineff=
       F       F
Bank Sta=5183.8,5188.2
XS Rating Curve= 0 ,0
Exp/Cntr=0.3,0.1

Type RM Length L Ch R = 1 ,89      ,0,0,0
BEGIN DESCRIPTION:
SANFERNANDO049 1.0
END DESCRIPTION:
XS GIS Cut Line= 4
       2812876.2     10284897.37      2812672.23     10284984.17
      2812667.06     10285114.68      2812832.74     10285808.49
#Sta/Elev= 30
  4640.9 1275.21  4692.1 1275.39  4821.2  1270.1  4850.2 1267.51  4971.6 1262.68
  4989.9 1259.87  5007.9 1259.77    5013 1261.65  5032.7 1259.85  5083.6 1259.86
  5092.1 1257.82  5097.2 1259.98  5114.9 1259.55  5133.5 1256.98  5139.3 1258.29
  5176.2 1257.42  5181.4 1258.52  5185.7  1256.6  5207.5 1257.93  5221.1 1254.69
  5221.4 1254.19  5225.8 1254.69  5265.6 1259.63  5270.7 1258.78  5289.7 1260.83
  5464.5 1263.84  5570.5 1269.07  5639.3 1277.33  5680.4 1281.13  5706.5 1282.04
#Mann= 6 ,-1 , 0
  4640.9     .12       0  5083.6     .05       0  5133.5     .12       0
  5185.7     .05       0  5221.1     .07       0  5225.8     .05       0
#XS Ineff= 2 , 0
         5013.18 1261.75 5309.77         1261.17
Permanent Ineff=
       F       F
Bank Sta=5221.1,5225.8
XS Rating Curve= 0 ,0
Exp/Cntr=0.3,0.1

Chan Stop Cuts=-1
Use User Specified Reach Order=0
Composite Channel Slope=5