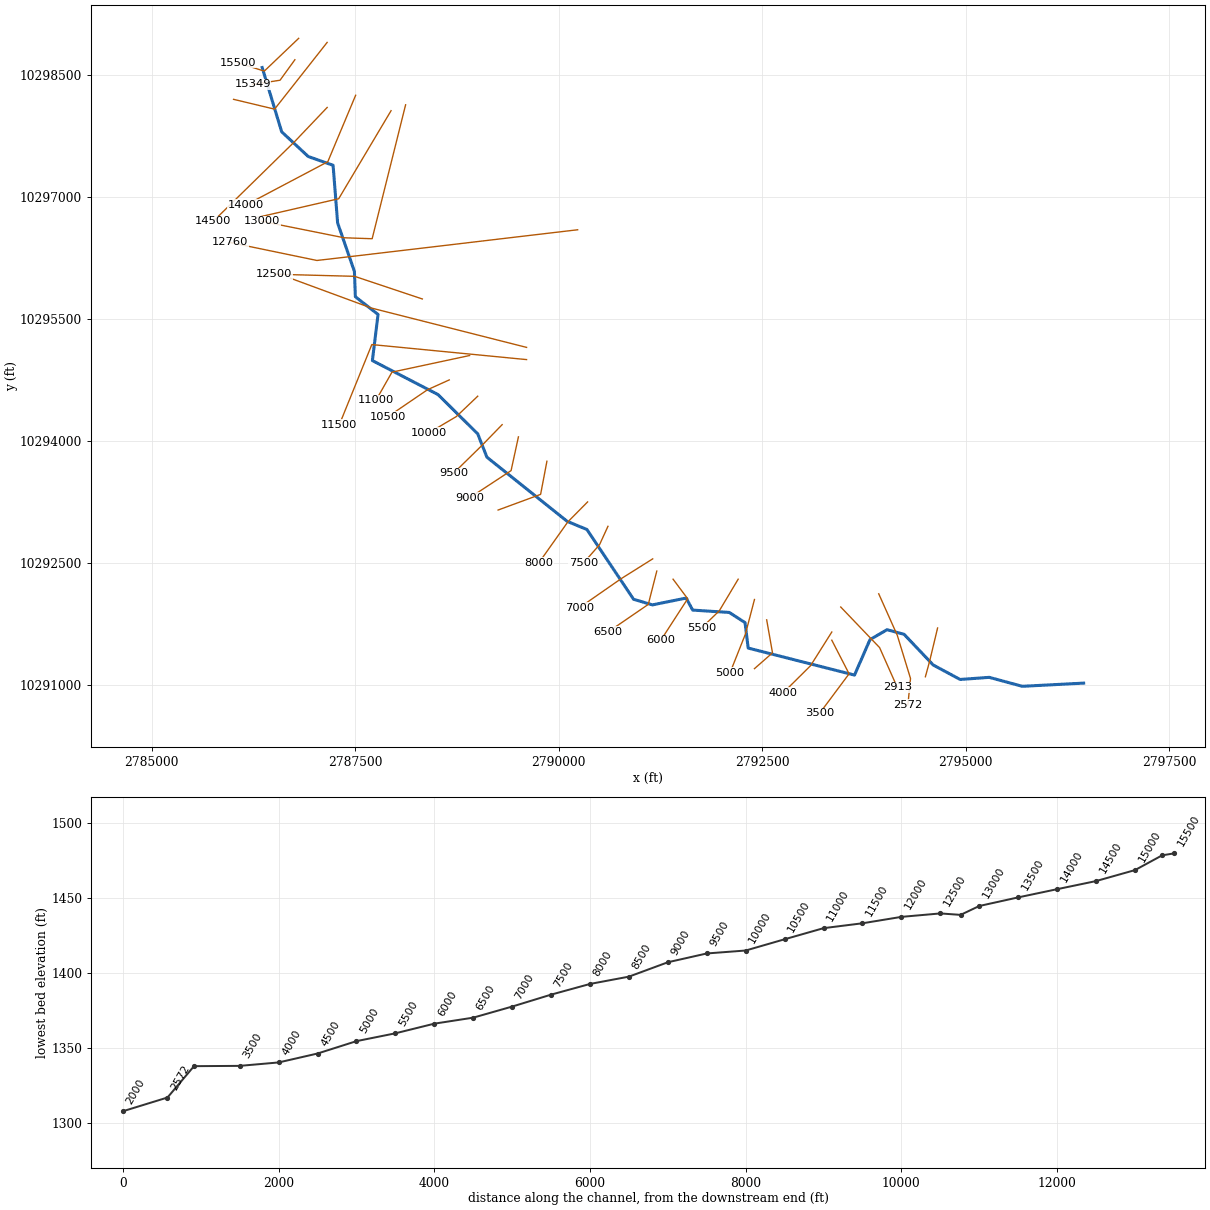
--- SANFERNANDO054.prj (project) ---

Proj Title=SANFERNANDO054 Base Level Engineering
Current Plan=p01
Default Exp/Contr=0.3,0.1
English Units
Geom File=g01
Flow File=f01
Plan File=p01
BEGIN DESCRIPTION:
SANFERNANDO054
END DESCRIPTION:

--- SANFERNANDO054.p01 (plan) ---

Plan Title=Multiple Run
Short Identifier=Multiple
Geom File=g01
Flow File=f01
Subcritical Flow
K Sum by GR= 0
Std Step Tol= 0.01
Critical Tol= 0.01
Num of Std Step Trials= 20
Max Error Tol= 0.3
Flow Tol Ratio= 0.001
Split Flow NTrial= 30
Split Flow Tol= 0.02
Split Flow Ratio= 0.02
Log Output Level= 0
Friction Slope Method= 1
Unsteady Friction Slope Method= 2
Unsteady Bridges Friction Slope Method= 1
Parabolic Critical Depth
Global Vel Dist=  1 , 1 , 1
Global Log Level= 0
CheckData=True
Encroach Param= -1, 0, 0, 0
BEGIN DESCRIPTION:
Multiple Run
END DESCRIPTION:

--- SANFERNANDO054.f01 (steady flow) ---

Flow Title=Multiple
Number of Profiles=7
Profile Names=10-year,25-year,50-year,1pct_min,100-year,1pct_plu,500-year
River Rch & RM= SANFERNANDO054,Reach-1,15500
     426     688     914     605    1216    2442    1669
River Rch & RM= SANFERNANDO054,Reach-1,6500
     663    1109    1607    1021    2199    4734    3064
Boundary for River Rch & Prof#=SANFERNANDO054,Reach-1,1
Up Type=0
Dn Type=3
Dn Slope=0.005
Boundary for River Rch & Prof#=SANFERNANDO054,Reach-1,2
Up Type=0
Dn Type=3
Dn Slope=0.005
Boundary for River Rch & Prof#=SANFERNANDO054,Reach-1,3
Up Type=0
Dn Type=3
Dn Slope=0.005
Boundary for River Rch & Prof#=SANFERNANDO054,Reach-1,4
Up Type=0
Dn Type=3
Dn Slope=0.005
Boundary for River Rch & Prof#=SANFERNANDO054,Reach-1,5
Up Type=0
Dn Type=3
Dn Slope=0.005
Boundary for River Rch & Prof#=SANFERNANDO054,Reach-1,6
Up Type=0
Dn Type=3
Dn Slope=0.005
Boundary for River Rch & Prof#=SANFERNANDO054,Reach-1,7
Up Type=0
Dn Type=3
Dn Slope=0.005

--- SANFERNANDO054.g01 (geometry) ---

Geom Title=Existing Conditions

River Reach=SANFERNANDO054,Reach-1
Reach XY= 30
      2786357.50     10298594.00      2786596.75     10297804.00
      2786923.00     10297500.00      2787228.50     10297392.00
      2787284.25     10296683.00      2787490.50     10296087.00
      2787502.25     10295776.00      2787780.75     10295558.00
      2787711.25     10294991.00      2788517.75     10294573.00
      2789006.25     10294089.00      2789118.25     10293803.00
      2790105.00     10293014.00      2790347.25     10292914.00
      2790920.25     10292056.00      2791152.75     10291987.00
      2791566.00     10292071.00      2791646.75     10291923.00
      2792096.50     10291894.00      2792290.00     10291769.00
      2792328.50     10291456.00      2793635.00     10291124.00
      2793825.00     10291560.00      2794034.75     10291682.00
      2794244.25     10291625.00      2794601.75     10291248.00
      2794932.50     10291070.00      2795290.00     10291096.00
      2795696.25     10290986.00      2796449.75     10291025.00

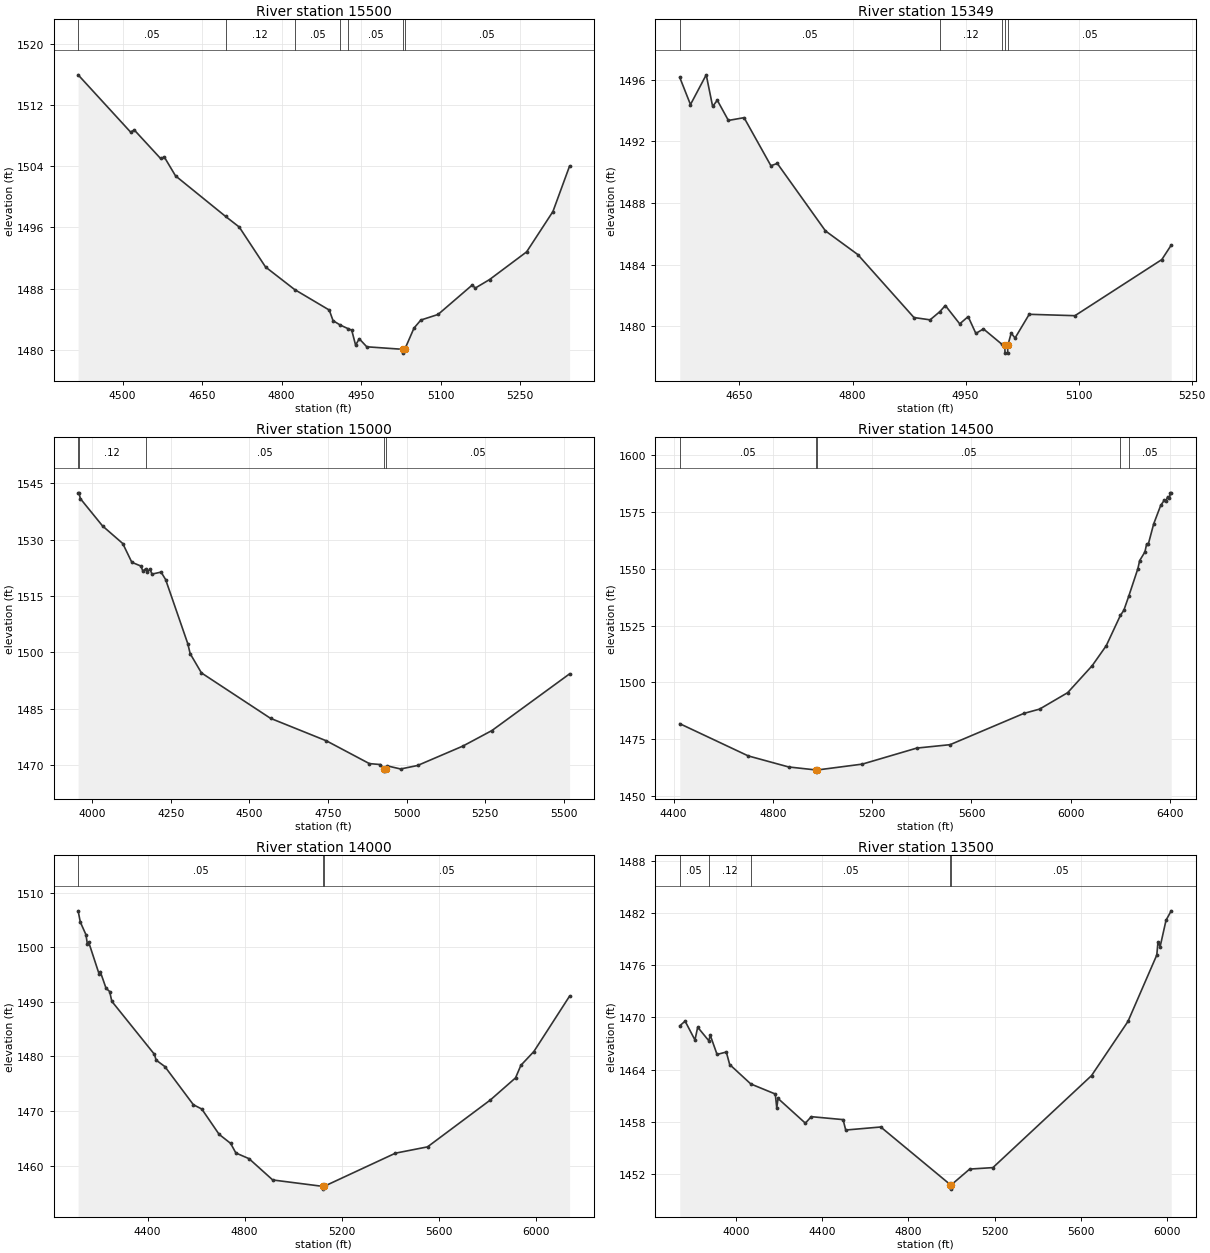
Type RM Length L Ch R = 1,15500,151,151,151
BEGIN DESCRIPTION:
SANFERNANDO054 31.0
END DESCRIPTION:
XS GIS Cut Line= 3
      2786805.66     10298953.09      2786383.27     10298550.09
      2786055.69     10298653.11
#Sta/Elev= 30
  4416.2 1515.98  4515.1 1508.49  4522.3 1508.75  4571.7 1505.03  4578.9 1505.21
  4600.0 1502.75  4694.6 1497.43  4720.2 1496.05  4769.8 1490.82  4824.6 1487.87
  4890.0 1485.18  4897.2 1483.79  4910.9 1483.21  4926.0 1482.73  4932.4 1482.55
  4939.7 1480.59  4946.6 1481.42  4960.8 1480.37  5028.5 1480.04  5028.7 1479.54
  5032.5 1480.04  5049.9 1482.82  5062.8 1483.87  5095.2 1484.60  5160.0 1488.47
  5165.3 1488.05  5192.4 1489.17  5262.4 1492.80  5312.0 1498.08  5343.4 1504.03
#Mann=7,-1,0
  4416.2    0.05       0  4694.6    0.12       0  4824.6    0.05       0
  4910.9    0.12       0  4926.0    0.05       0  5028.5    0.05       0
  5032.5    0.05       0
Bank Sta=5028.5,5032.5
Exp/Cntr=0.3,0.1

Type RM Length L Ch R = 1,15349,349,349,349
BEGIN DESCRIPTION:
Mapping XS b99f1df3
END DESCRIPTION:
XS GIS Cut Line= 3
      2786758.97     10298689.66      2786576.68     10298437.92
      2786239.46     10298386.04
#Sta/Elev= 30
  4570.8 1496.14  4585.0 1494.38  4605.9 1496.31  4614.4 1494.26  4620.6 1494.66
  4635.3 1493.35  4656.1 1493.53  4691.7 1490.41  4700.2 1490.56  4764.1 1486.18
  4806.9 1484.65  4881.5 1480.56  4902.9 1480.41  4915.8 1480.94  4923.1 1481.34
  4942.2 1480.15  4953.4 1480.62  4963.6 1479.53  4973.7 1479.82  4997.8 1478.84
  5002.0 1478.75  5002.3 1478.25  5005.8 1478.25  5006.0 1478.75  5010.5 1479.55
  5015.6 1479.23  5034.4 1480.77  5095.1 1480.68  5210.3 1484.32  5222.8 1485.26
#Mann=5,-1,0
  4570.8    0.05       0  4915.8    0.12       0  4997.8    0.05       0
  5002.0    0.03       0  5006.0    0.05       0
Bank Sta=5002,5006
Exp/Cntr=0.3,0.1

Type RM Length L Ch R = 1,15000,500,500,500
BEGIN DESCRIPTION:
SANFERNANDO054 30.0
END DESCRIPTION:
XS GIS Cut Line= 3
      2787155.67     10298903.09      2786509.66     10298082.46
      2786005.70     10298203.11
#Sta/Elev= 30
  3955.6 1542.44  3958.3 1542.44  3962.8 1540.89  4033.3 1533.63  4097.5 1528.96
  4126.4 1523.96  4155.3 1522.96  4161.6 1521.59  4170.1 1522.23  4176.1 1521.38
  4184.1 1522.15  4190.5 1520.82  4219.4 1521.35  4233.9 1519.36  4304.4 1502.29
  4311.9 1499.66  4347.7 1494.54  4567.3 1482.46  4745.3 1476.46  4881.7 1470.41
  4917.0 1470.16  4929.4 1468.91  4929.7 1468.41  4933.4 1468.91  4937.8 1469.82
  4981.1 1468.98  5034.9 1469.91  5178.9 1475.07  5271.4 1479.21  5518.2 1494.28
#Mann=5,-1,0
  3955.6    0.05       0  3958.3    0.12       0  4170.1    0.05       0
  4929.4    0.05       0  4933.4    0.05       0
Bank Sta=4929.4,4933.4
Exp/Cntr=0.3,0.1

Type RM Length L Ch R = 1,14500,500,500,500
BEGIN DESCRIPTION:
SANFERNANDO054 29.0
END DESCRIPTION:
XS GIS Cut Line= 3
      2787155.71     10298103.14      2786759.09     10297686.28
      2785755.68     10296703.10
#Sta/Elev= 30
  4424.6 1481.92  4700.7 1467.77  4863.3 1462.93  4974.5 1461.60  4974.8 1461.10
  4978.5 1461.60  5160.2 1464.18  5379.5 1471.21  5513.8 1472.71  5810.8 1486.42
  5874.4 1488.32  5987.5 1495.53  6086.5 1507.40  6143.1 1516.16  6200.0 1529.45
  6213.8 1531.65  6233.7 1537.89  6270.4 1549.94  6277.6 1553.49  6298.7 1557.27
  6305.9 1560.81  6312.9 1560.88  6334.1 1569.59  6362.4 1577.70  6376.6 1579.95
  6383.6 1579.68  6390.7 1581.59  6397.7 1580.93  6401.3 1583.23  6404.8 1583.23
#Mann=5,-1,0
  4424.6    0.05       0  4974.5    0.03       0  4978.5    0.05       0
  6200.0    0.12       0  6233.7    0.05       0
Bank Sta=4974.5,4978.5
Exp/Cntr=0.3,0.1

Type RM Length L Ch R = 1,14000,500,500,500
BEGIN DESCRIPTION:
SANFERNANDO054 28.0
END DESCRIPTION:
XS GIS Cut Line= 3
      2787505.67     10298253.07      2787163.39     10297435.63
      2786155.65     10296903.09
#Sta/Elev= 30
  4113.8 1506.67  4122.9 1504.61  4146.3 1502.28  4152.1 1500.51  4157.6 1500.89
  4199.7 1495.18  4205.1 1495.54  4228.9 1492.49  4243.8 1491.89  4252.7 1490.10
  4428.1 1480.40  4435.5 1479.32  4471.5 1478.14  4589.0 1471.15  4623.7 1470.36
  4695.0 1465.73  4742.5 1464.07  4764.2 1462.31  4818.4 1461.27  4916.0 1457.37
  5123.3 1456.19  5123.5 1455.69  5127.3 1456.19  5422.2 1462.28  5554.2 1463.43
  5812.7 1472.00  5917.1 1476.07  5939.1 1478.37  5992.7 1480.90  6139.8 1491.04
#Mann=3,-1,0
  4113.8    0.05       0  5123.3    0.03       0  5127.3    0.05       0
Bank Sta=5123.3,5127.3
Exp/Cntr=0.3,0.1

Type RM Length L Ch R = 1,13500,500,500,500
BEGIN DESCRIPTION:
SANFERNANDO054 27.0
END DESCRIPTION:
XS GIS Cut Line= 3
      2787940.80     10298063.52      2787297.48     10296980.94
      2786305.71     10296753.12
#Sta/Elev= 30
  3740.7 1469.04  3765.4 1469.58  3811.0 1467.41  3823.8 1468.88  3874.8 1467.33
  3882.3 1467.93  3913.5 1465.74  3956.3 1466.02  3971.9 1464.58  4069.7 1462.34
  4183.2 1461.18  4190.1 1459.58  4195.9 1460.67  4322.6 1457.82  4349.8 1458.57
  4497.3 1458.23  4509.5 1457.03  4671.8 1457.38  4994.9 1450.72  4995.1 1450.22
  4998.9 1450.72  5083.9 1452.53  5191.5 1452.70  5648.3 1463.30  5817.1 1469.54
  5950.8 1477.20  5956.1 1478.66  5966.3 1478.17  5993.6 1481.21  6017.6 1482.29
#Mann=5,-1,0
  3740.7    0.05       0  3874.8    0.12       0  4069.7    0.05       0
  4994.9    0.03       0  4998.9    0.05       0
Bank Sta=4994.9,4998.9
Exp/Cntr=0.3,0.1

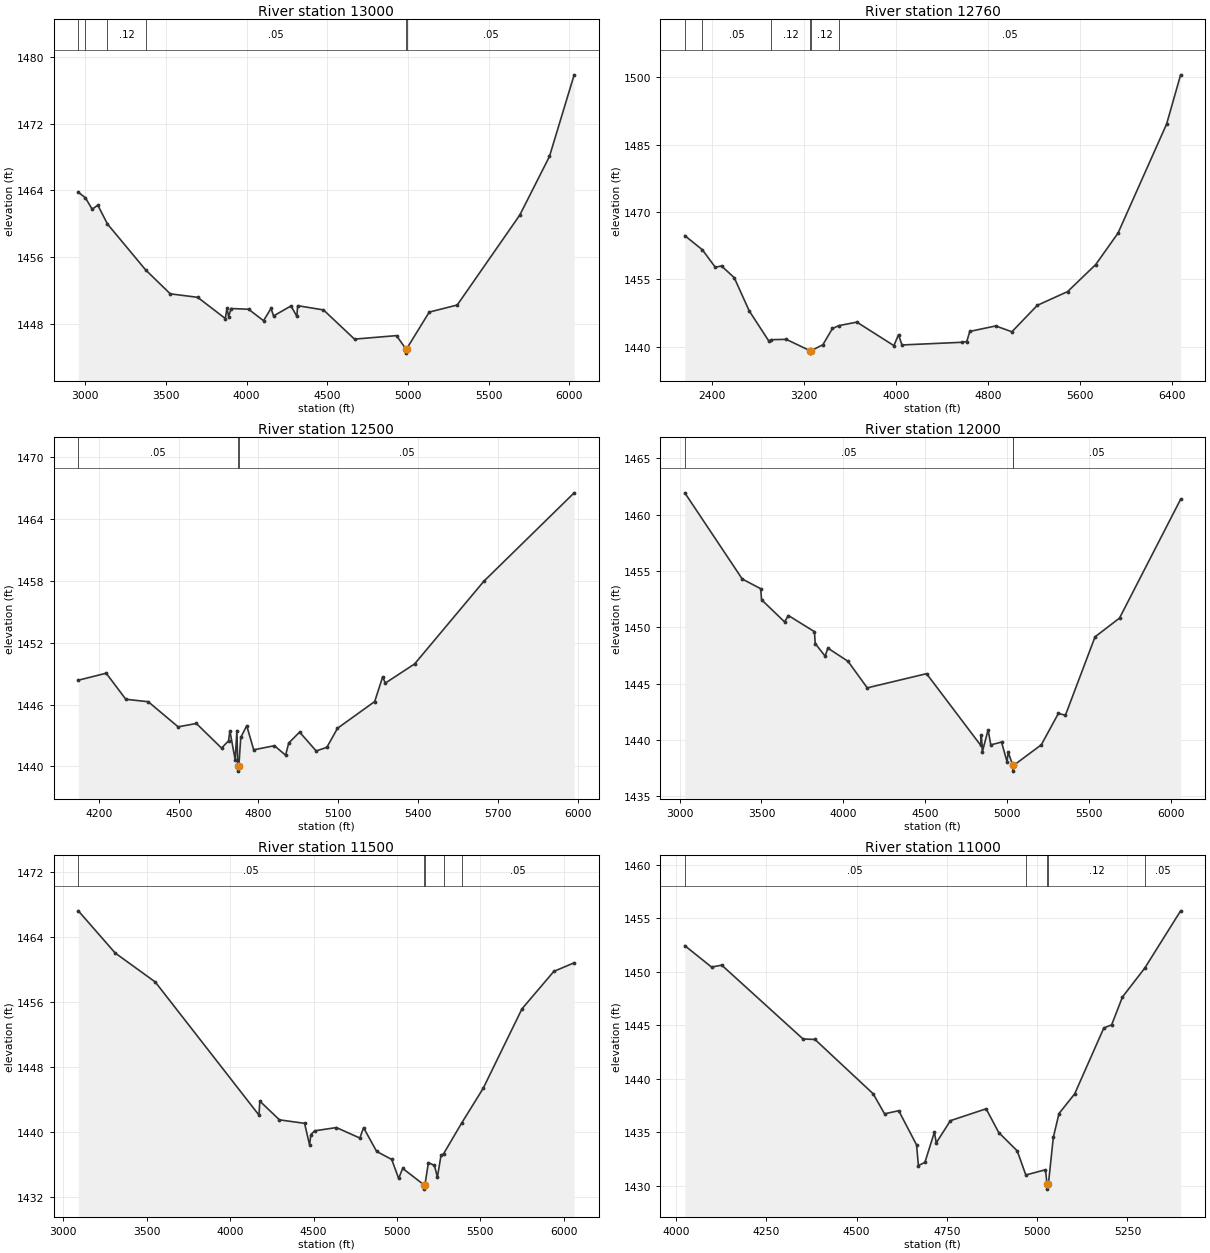
Type RM Length L Ch R = 1,13000,240,240,240
BEGIN DESCRIPTION:
SANFERNANDO054 26.0
END DESCRIPTION:
XS GIS Cut Line= 4
      2788119.60     10298136.19      2787708.49     10296489.19
      2787364.72     10296500.81      2786355.70     10296703.11
#Sta/Elev= 30
  2958.5 1463.77  3002.2 1463.11  3044.1 1461.74  3079.1 1462.22  3139.0 1459.96
  3375.3 1454.46  3527.8 1451.59  3697.9 1451.17  3868.7 1448.63  3879.0 1449.87
  3889.3 1448.84  3904.2 1449.83  4013.0 1449.74  4105.4 1448.37  4151.8 1449.84
  4167.6 1448.94  4275.6 1450.14  4311.7 1448.89  4316.8 1450.17  4476.7 1449.66
  4668.8 1446.16  4929.0 1446.58  4987.0 1444.98  4987.3 1444.48  4991.0 1444.98
  5131.6 1449.40  5305.0 1450.25  5692.5 1461.04  5876.1 1468.06  6029.1 1477.85
#Mann=6,-1,0
  2958.5    0.12       0  3002.2    0.05       0  3139.0    0.12       0
  3375.3    0.05       0  4987.0    0.03       0  4991.0    0.05       0
Bank Sta=4987,4991
Exp/Cntr=0.3,0.1

Type RM Length L Ch R = 1,12760,260,260,260
BEGIN DESCRIPTION:
Mapping XS 5dc5951e
END DESCRIPTION:
XS GIS Cut Line= 4
      2790233.05     10296599.43      2787589.86     10296286.93
      2787029.96     10296221.83      2785962.24     10296443.19
#Sta/Elev= 30
  2162.4 1464.75  2315.6 1461.59  2427.9 1457.70  2482.0 1457.99  2592.7 1455.38
  2723.6 1447.96  2894.8 1441.22  2916.6 1441.56  3045.9 1441.63  3255.3 1439.06
  3255.6 1438.56  3259.3 1439.06  3364.5 1440.44  3447.4 1444.05  3503.3 1444.69
  3660.1 1445.47  3982.4 1440.23  4022.6 1442.67  4052.8 1440.38  4576.5 1440.98
  4616.7 1441.14  4642.8 1443.40  4868.5 1444.62  5009.4 1443.32  5230.9 1449.22
  5494.2 1452.27  5739.3 1458.31  5933.3 1465.32  6355.9 1489.61  6478.1 1500.59
#Mann=6,-1,0
  2162.4    0.12       0  2315.6    0.05       0  2916.6    0.12       0
  3255.3    0.03       0  3259.3    0.12       0  3503.3    0.05       0
Bank Sta=3255.3,3259.3
Exp/Cntr=0.3,0.1

Type RM Length L Ch R = 1,12500,500,500,500
BEGIN DESCRIPTION:
SANFERNANDO054 25.0
END DESCRIPTION:
XS GIS Cut Line= 3
      2788325.08     10295748.42      2787492.72     10296026.86
      2786505.67     10296053.11
#Sta/Elev= 30
  4122.3 1448.36  4227.1 1449.04  4300.9 1446.51  4385.3 1446.27  4497.8 1443.83
  4566.2 1444.16  4661.0 1441.77  4687.3 1442.47  4692.5 1443.44  4712.2 1440.63
  4718.8 1443.46  4722.1 1440.03  4722.4 1439.53  4726.1 1440.03  4733.3 1442.80
  4755.7 1443.94  4782.0 1441.60  4859.8 1442.00  4902.0 1441.08  4913.6 1442.26
  4954.7 1443.32  5017.0 1441.49  5057.1 1441.84  5097.1 1443.69  5237.1 1446.29
  5267.1 1448.69  5277.1 1448.08  5387.2 1449.94  5647.3 1457.96  5987.4 1466.56
#Mann=3,-1,0
  4122.3    0.05       0  4722.1    0.03       0  4726.1    0.05       0
Bank Sta=4722.1,4726.1
Exp/Cntr=0.3,0.1

Type RM Length L Ch R = 1,12000,500,500,500
BEGIN DESCRIPTION:
SANFERNANDO054 24.0
END DESCRIPTION:
XS GIS Cut Line= 3
      2789605.65     10295153.12      2787698.39     10295637.10
      2786705.72     10296003.10
#Sta/Elev= 30
  3032.3 1461.93  3383.0 1454.28  3495.6 1453.42  3500.7 1452.44  3641.0 1450.48
  3664.6 1451.04  3823.3 1449.61  3828.4 1448.55  3888.6 1447.44  3905.2 1448.15
  4028.1 1446.98  4145.8 1444.62  4507.6 1445.88  4837.0 1439.54  4842.2 1440.45
  4848.0 1438.93  4883.2 1440.90  4899.6 1439.56  4965.1 1439.81  4998.8 1438.06
  5005.6 1438.92  5034.0 1437.73  5034.3 1437.23  5038.0 1437.73  5208.0 1439.57
  5312.0 1442.35  5354.9 1442.19  5535.8 1449.15  5685.0 1450.81  6058.0 1461.36
#Mann=3,-1,0
  3032.3    0.05       0  5034.0    0.03       0  5038.0    0.05       0
Bank Sta=5034,5038
Exp/Cntr=0.3,0.1

Type RM Length L Ch R = 1,11500,500,500,500
BEGIN DESCRIPTION:
SANFERNANDO054 23.0
END DESCRIPTION:
XS GIS Cut Line= 3
      2789605.71     10295003.11      2787704.36     10295187.79
      2787305.69     10294203.13
#Sta/Elev= 30
  3089.7 1467.18  3310.8 1461.99  3551.0 1458.43  4172.8 1442.06  4177.8 1443.78
  4295.4 1441.48  4446.1 1441.05  4476.2 1438.38  4483.7 1439.66  4506.4 1440.13
  4637.0 1440.53  4777.6 1439.24  4799.6 1440.52  4878.1 1437.60  4968.5 1436.61
  5010.1 1434.27  5034.2 1435.51  5163.6 1433.46  5163.8 1432.96  5167.6 1433.46
  5188.4 1436.22  5224.6 1435.87  5242.4 1434.44  5264.0 1437.10  5279.5 1437.31
  5387.4 1441.07  5516.8 1445.35  5749.5 1455.13  5940.3 1459.73  6062.3 1460.79
#Mann=5,-1,0
  3089.7    0.05       0  5163.6    0.05       0  5167.6    0.05       0
  5279.5    0.12       0  5387.4    0.05       0
Bank Sta=5163.6,5167.6
Exp/Cntr=0.3,0.1

Type RM Length L Ch R = 1,11000,500,500,500
BEGIN DESCRIPTION:
SANFERNANDO054 22.0
END DESCRIPTION:
XS GIS Cut Line= 3
      2788905.68     10295053.11      2787951.94     10294848.70
      2787755.70     10294503.14
#Sta/Elev= 30
  4024.6 1452.44  4098.7 1450.44  4126.9 1450.62  4351.9 1443.73  4385.1 1443.68
  4546.2 1438.61  4577.7 1436.74  4616.9 1437.03  4666.3 1433.84  4671.4 1431.91
  4689.4 1432.21  4715.7 1435.03  4720.8 1434.03  4760.0 1436.10  4858.9 1437.21
  4893.9 1434.99  4945.0 1433.28  4968.8 1431.03  5023.2 1431.52  5027.4 1430.21
  5027.7 1429.71  5031.4 1430.21  5044.9 1434.54  5060.7 1436.77  5104.0 1438.60
  5184.7 1444.75  5206.4 1445.05  5236.4 1447.65  5298.0 1450.34  5397.4 1455.69
#Mann=5,-1,0
  4024.6    0.05       0  4968.8    0.12       0  5027.4    0.07       0
  5031.4    0.12       0  5298.0    0.05       0
Bank Sta=5027.4,5031.4
Exp/Cntr=0.3,0.1

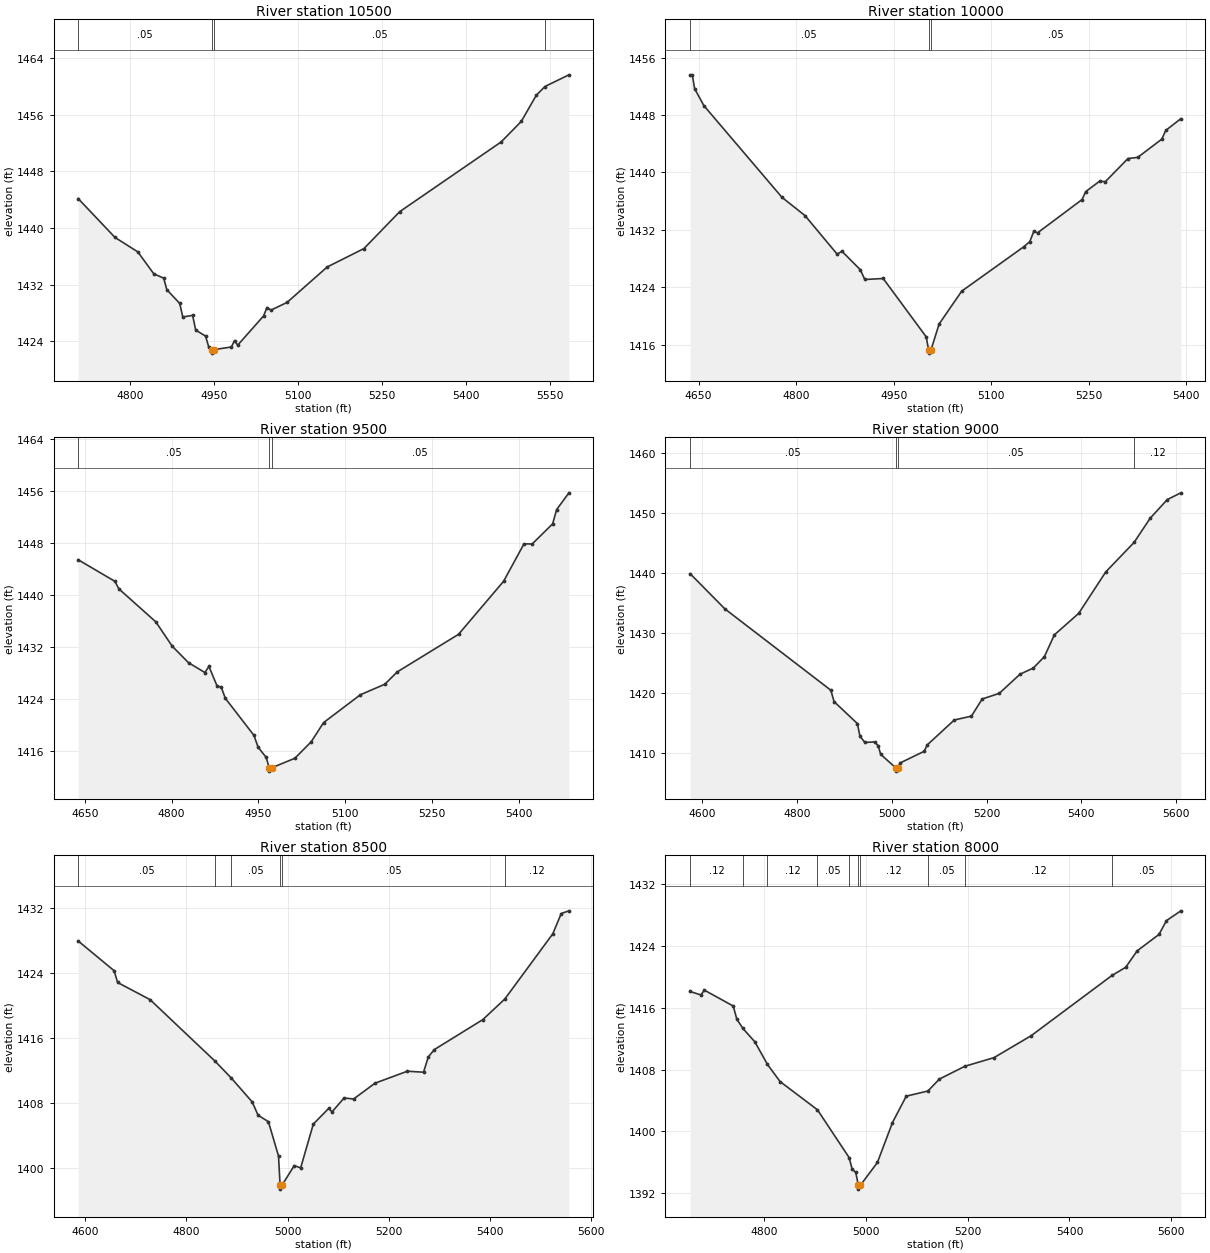
Type RM Length L Ch R = 1,10500,500,500,500
BEGIN DESCRIPTION:
SANFERNANDO054 21.0
END DESCRIPTION:
XS GIS Cut Line= 3
      2788655.69     10294753.11      2788388.44     10294632.50
      2787905.71     10294303.13
#Sta/Elev= 30
  4706.8 1444.15  4772.8 1438.65  4813.6 1436.61  4842.2 1433.51  4859.9 1432.90
  4865.4 1431.28  4888.5 1429.33  4894.0 1427.42  4911.6 1427.64  4917.1 1425.56
  4934.7 1424.72  4940.2 1423.23  4946.2 1422.81  4946.4 1422.31  4950.2 1422.81
  4981.0 1423.18  4986.5 1424.09  4992.1 1423.43  5038.4 1427.56  5044.5 1428.75
  5051.8 1428.39  5080.4 1429.47  5152.2 1434.48  5217.9 1437.08  5281.8 1442.29
  5463.2 1452.14  5499.1 1455.03  5526.1 1458.74  5541.5 1459.97  5584.4 1461.62
#Mann=4,-1,0
  4706.8    0.05       0  4946.2    0.05       0  4950.2    0.05       0
  5541.5    0.12       0
Bank Sta=4946.2,4950.2
Exp/Cntr=0.3,0.1

Type RM Length L Ch R = 1,10000,500,500,500
BEGIN DESCRIPTION:
SANFERNANDO054 20.0
END DESCRIPTION:
XS GIS Cut Line= 3
      2789005.70     10294553.12      2788742.70     10294302.49
      2788405.66     10294103.10
#Sta/Elev= 30
  4636.7 1453.59  4640.2 1453.59  4643.8 1451.66  4658.0 1449.30  4778.1 1436.52
  4813.6 1433.97  4863.0 1428.60  4870.3 1429.01  4898.6 1426.43  4905.5 1425.07
  4933.8 1425.21  5000.0 1417.07  5003.5 1415.31  5003.7 1414.81  5007.5 1415.31
  5019.8 1418.87  5054.6 1423.45  5149.7 1429.61  5159.2 1430.34  5165.4 1431.77
  5171.2 1431.57  5239.5 1436.20  5245.3 1437.32  5266.7 1438.77  5275.4 1438.70
  5310.2 1441.92  5325.3 1442.09  5362.3 1444.63  5368.3 1445.84  5391.6 1447.48
#Mann=3,-1,0
  4636.7    0.05       0  5003.5    0.05       0  5007.5    0.05       0
Bank Sta=5003.5,5007.5
Exp/Cntr=0.3,0.1

Type RM Length L Ch R = 1,9500,500,500,500
BEGIN DESCRIPTION:
SANFERNANDO054 19.0
END DESCRIPTION:
XS GIS Cut Line= 3
      2789305.66     10294203.08      2789053.26     10293943.86
      2788705.72     10293603.14
#Sta/Elev= 30
  4638.2 1445.41  4701.8 1442.08  4708.8 1440.91  4772.5 1435.84  4800.8 1432.10
  4829.1 1429.54  4857.4 1428.03  4864.4 1428.97  4878.5 1425.95  4885.7 1425.77
  4892.7 1424.06  4942.3 1418.34  4949.3 1416.54  4963.4 1414.95  4968.6 1413.34
  4968.8 1412.84  4972.6 1413.34  5012.9 1414.82  5041.2 1417.36  5062.5 1420.31
  5126.1 1424.60  5168.5 1426.23  5189.8 1428.12  5295.8 1433.91  5373.7 1442.08
  5409.0 1447.85  5423.1 1447.83  5458.5 1450.93  5465.5 1453.14  5486.7 1455.71
#Mann=3,-1,0
  4638.2    0.05       0  4968.6    0.05       0  4972.6    0.05       0
Bank Sta=4968.6,4972.6
Exp/Cntr=0.3,0.1

Type RM Length L Ch R = 1,9000,500,500,500
BEGIN DESCRIPTION:
SANFERNANDO054 18.0
END DESCRIPTION:
XS GIS Cut Line= 3
      2789505.69     10294053.13      2789415.25     10293637.86
      2788905.67     10293303.10
#Sta/Elev= 30
  4575.0 1439.89  4648.6 1434.00  4871.8 1420.46  4878.7 1418.56  4927.8 1414.90
  4933.2 1412.81  4943.5 1411.76  4963.9 1411.84  4971.7 1411.22  4976.9 1409.78
  5009.4 1407.48  5009.7 1406.98  5013.4 1407.48  5017.6 1408.33  5068.8 1410.29
  5074.8 1411.33  5132.1 1415.50  5168.2 1416.14  5190.9 1419.00  5226.8 1419.93
  5270.7 1423.13  5298.6 1424.15  5322.0 1426.05  5343.0 1429.68  5394.3 1433.26
  5451.5 1440.18  5511.0 1445.07  5544.9 1449.10  5581.1 1452.22  5609.7 1453.34
#Mann=4,-1,0
  4575.0    0.05       0  5009.4    0.05       0  5013.4    0.05       0
  5511.0    0.12       0
Bank Sta=5009.4,5013.4
Exp/Cntr=0.3,0.1

Type RM Length L Ch R = 1,8500,500,500,500
BEGIN DESCRIPTION:
SANFERNANDO054 17.0
END DESCRIPTION:
XS GIS Cut Line= 3
      2789855.69     10293753.13      2789778.27     10293345.93
      2789255.70     10293153.12
#Sta/Elev= 30
  4585.5 1427.94  4656.8 1424.27  4663.8 1422.82  4728.0 1420.71  4856.7 1413.13
  4888.3 1411.09  4930.0 1408.13  4941.8 1406.48  4962.2 1405.69  4982.2 1401.46
  4985.3 1397.89  4985.6 1397.39  4989.3 1397.89  5013.4 1400.29  5026.0 1400.00
  5051.1 1405.40  5081.5 1407.32  5088.0 1406.89  5112.0 1408.61  5130.7 1408.48
  5173.3 1410.43  5237.2 1411.90  5269.2 1411.78  5278.6 1413.65  5290.5 1414.56
  5386.5 1418.25  5430.0 1420.78  5525.0 1428.81  5541.8 1431.31  5557.0 1431.64
#Mann=6,-1,0
  4585.5    0.05       0  4856.7    0.12       0  4888.3    0.05       0
  4985.3    0.05       0  4989.3    0.05       0  5430.0    0.12       0
Bank Sta=4985.3,4989.3
Exp/Cntr=0.3,0.1

Type RM Length L Ch R = 1,8000,500,500,500
BEGIN DESCRIPTION:
SANFERNANDO054 16.0
END DESCRIPTION:
XS GIS Cut Line= 3
      2790355.69     10293253.12      2790113.27     10293008.06
      2789755.71     10292503.15
#Sta/Elev= 30
  4655.3 1418.10  4676.5 1417.66  4683.6 1418.27  4740.1 1416.22  4747.2 1414.51
  4759.2 1413.31  4782.6 1411.58  4807.3 1408.66  4832.1 1406.44  4905.4 1402.79
  4967.6 1396.60  4973.5 1395.11  4980.6 1394.68  4985.7 1393.02  4985.9 1392.52
  4989.7 1393.02  5023.1 1395.97  5052.7 1401.14  5079.7 1404.55  5122.2 1405.22
  5144.9 1406.77  5194.7 1408.42  5252.0 1409.54  5324.7 1412.37  5483.6 1420.18
  5510.4 1421.23  5533.0 1423.37  5575.7 1425.48  5590.4 1427.27  5618.7 1428.54
#Mann=10,-1,0
  4655.3    0.12       0  4759.2    0.05       0  4807.3    0.12       0
  4905.4    0.05       0  4967.6    0.12       0  4985.7    0.07       0
  4989.7    0.12       0  5122.2    0.05       0  5194.7    0.12       0
  5483.6    0.05       0
Bank Sta=4985.7,4989.7
Exp/Cntr=0.3,0.1

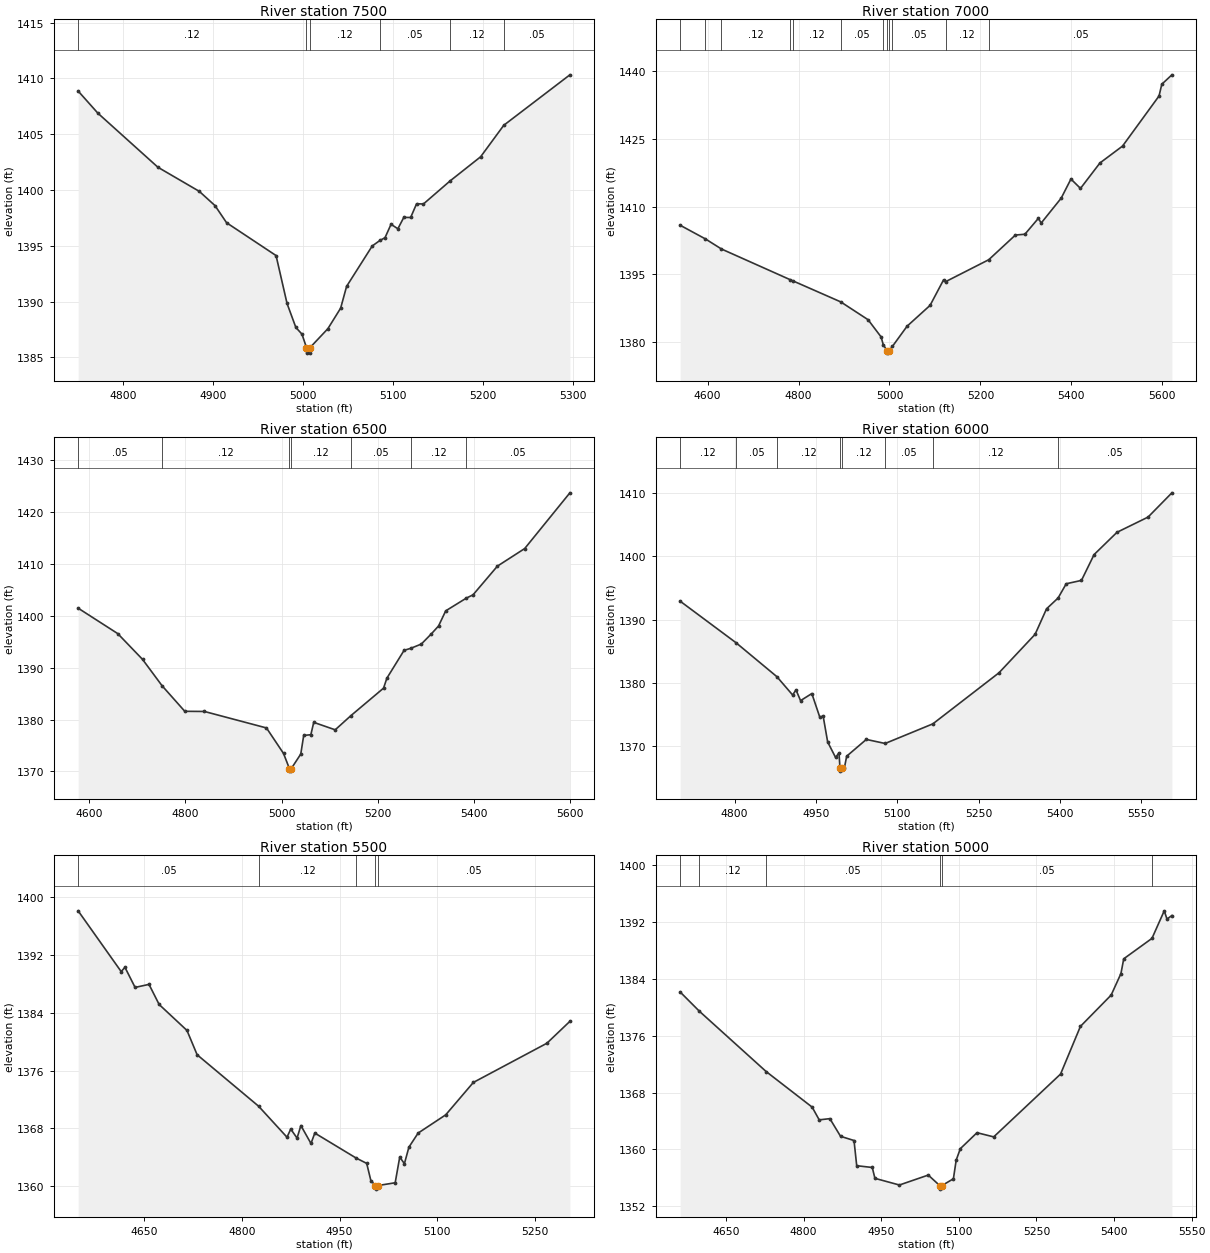
Type RM Length L Ch R = 1,7500,500,500,500
BEGIN DESCRIPTION:
SANFERNANDO054 15.0
END DESCRIPTION:
XS GIS Cut Line= 3
      2790605.67     10292953.09      2790501.43     10292725.75
      2790305.65     10292503.08
#Sta/Elev= 30
  4749.9 1408.87  4771.9 1406.88  4838.6 1402.04  4884.6 1399.88  4902.1 1398.60
  4914.9 1397.07  4969.9 1394.13  4982.1 1389.84  4991.9 1387.69  4998.7 1387.09
  5003.7 1385.89  5003.9 1385.39  5007.4 1385.39  5007.7 1385.89  5027.5 1387.58
  5041.7 1389.42  5048.3 1391.37  5076.8 1394.99  5085.3 1395.48  5091.0 1395.73
  5097.7 1396.93  5105.3 1396.53  5111.9 1397.55  5119.5 1397.54  5126.1 1398.77
  5133.7 1398.75  5163.4 1400.82  5197.3 1402.98  5223.0 1405.80  5296.5 1410.32
#Mann=6,-1,0
  4749.9    0.12       0  5003.7    0.07       0  5007.7    0.12       0
  5085.3    0.05       0  5163.4    0.12       0  5223.0    0.05       0
Bank Sta=5003.7,5007.7
Exp/Cntr=0.3,0.1

Type RM Length L Ch R = 1,7000,500,500,500
BEGIN DESCRIPTION:
SANFERNANDO054 14.0
END DESCRIPTION:
XS GIS Cut Line= 3
      2791155.68     10292553.11      2790765.78     10292307.89
      2790255.72     10291953.14
#Sta/Elev= 30
  4539.4 1405.85  4595.2 1402.80  4630.3 1400.57  4780.9 1393.78  4788.2 1393.46
  4892.8 1388.82  4952.9 1384.86  4981.6 1381.03  4986.2 1379.33  4994.9 1377.94
  4995.1 1377.44  4998.9 1377.94  5006.6 1378.96  5038.7 1383.42  5089.3 1388.05
  5119.0 1393.72  5123.4 1393.31  5218.4 1398.19  5277.0 1403.67  5297.9 1403.85
  5327.6 1407.39  5333.7 1406.33  5377.7 1411.86  5399.2 1416.11  5420.2 1414.03
  5463.0 1419.68  5512.7 1423.43  5593.0 1434.56  5599.1 1437.17  5621.3 1439.26
#Mann=12,-1,0
  4539.4    0.12       0  4595.2    0.05       0  4630.3    0.12       0
  4780.9    0.05       0  4788.2    0.12       0  4892.8    0.05       0
  4986.2    0.12       0  4994.9    0.07       0  4998.9    0.12       0
  5006.6    0.05       0  5123.4    0.12       0  5218.4    0.05       0
Bank Sta=4994.9,4998.9
Exp/Cntr=0.3,0.1

Type RM Length L Ch R = 1,6500,500,500,500
BEGIN DESCRIPTION:
SANFERNANDO054 13.0
END DESCRIPTION:
XS GIS Cut Line= 3
      2791205.67     10292403.08      2791100.89     10291992.74
      2790605.67     10291653.10
#Sta/Elev= 30
  4576.5 1401.49  4659.0 1396.58  4710.6 1391.61  4751.4 1386.51  4798.6 1381.59
  4839.4 1381.56  4968.7 1378.38  5004.2 1373.46  5016.4 1370.55  5016.7 1370.05
  5020.4 1370.55  5040.1 1373.34  5046.2 1376.93  5061.1 1377.08  5067.1 1379.46
  5111.8 1378.02  5144.7 1380.77  5212.5 1386.06  5219.4 1387.98  5255.3 1393.36
  5268.8 1393.73  5291.2 1394.57  5312.1 1396.54  5327.0 1398.05  5341.9 1400.97
  5385.1 1403.44  5398.8 1404.06  5449.6 1409.60  5506.4 1412.99  5600.5 1423.74
#Mann=7,-1,0
  4576.5    0.05       0  4751.4    0.12       0  5016.4    0.07       0
  5020.4    0.12       0  5144.7    0.05       0  5268.8    0.12       0
  5385.1    0.05       0
Bank Sta=5016.4,5020.4
Exp/Cntr=0.3,0.1

Type RM Length L Ch R = 1,6000,500,500,500
BEGIN DESCRIPTION:
SANFERNANDO054 12.0
END DESCRIPTION:
XS GIS Cut Line= 3
      2791405.67     10292303.13      2791585.27     10292062.21
      2791255.67     10291553.09
#Sta/Elev= 30
  4699.5 1392.90  4802.6 1386.33  4877.9 1380.97  4907.0 1378.07  4913.2 1378.88
  4921.6 1377.18  4942.4 1378.30  4957.0 1374.59  4963.3 1374.73  4971.6 1370.65
  4986.2 1368.20  4992.5 1368.93  4994.3 1366.54  4994.6 1366.04  4998.3 1366.54
  5002.4 1366.54  5006.7 1368.40  5042.9 1371.05  5077.6 1370.41  5165.6 1373.51
  5287.6 1381.58  5354.2 1387.66  5375.3 1391.69  5396.6 1393.40  5411.6 1395.65
  5439.7 1396.18  5463.0 1400.26  5505.2 1403.78  5562.6 1406.19  5606.5 1410.02
#Mann=8,-1,0
  4699.5    0.12       0  4802.6    0.05       0  4877.9    0.12       0
  4994.3    0.07       0  4998.3    0.12       0  5077.6    0.05       0
  5165.6    0.12       0  5396.6    0.05       0
Bank Sta=4994.3,4998.3
Exp/Cntr=0.3,0.1

Type RM Length L Ch R = 1,5500,500,500,500
BEGIN DESCRIPTION:
SANFERNANDO054 11.0
END DESCRIPTION:
XS GIS Cut Line= 3
      2792205.71     10292303.15      2791974.09     10291915.00
      2791755.68     10291703.11
#Sta/Elev= 30
  4548.0 1398.09  4614.2 1389.69  4620.0 1390.28  4635.6 1387.50  4657.0 1387.92
  4672.6 1385.14  4715.4 1381.55  4731.0 1378.19  4825.5 1371.08  4869.2 1366.79
  4875.0 1367.91  4884.7 1366.67  4890.6 1368.40  4906.1 1365.92  4912.0 1367.36
  4975.7 1363.90  4991.8 1363.17  4998.2 1360.79  5005.3 1360.11  5005.5 1359.61
  5009.4 1360.11  5035.6 1360.49  5042.6 1364.04  5049.8 1363.13  5056.7 1365.41
  5070.9 1367.36  5113.3 1369.88  5155.8 1374.36  5268.9 1379.78  5304.3 1382.81
#Mann=5,-1,0
  4548.0    0.05       0  4825.5    0.12       0  4975.7    0.05       0
  5005.3    0.05       0  5009.4    0.05       0
Bank Sta=5005.3,5009.4
Exp/Cntr=0.3,0.1

Type RM Length L Ch R = 1,5000,500,500,500
BEGIN DESCRIPTION:
SANFERNANDO054 10.0
END DESCRIPTION:
XS GIS Cut Line= 3
      2792405.69     10292053.14      2792294.78     10291628.69
      2792105.68     10291153.10
#Sta/Elev= 30
  4561.3 1382.17  4598.4 1379.46  4727.5 1370.96  4816.5 1365.94  4830.1 1364.15
  4850.7 1364.32  4871.4 1361.83  4897.4 1361.24  4902.6 1357.69  4932.7 1357.44
  4937.8 1355.91  4985.1 1354.97  5040.9 1356.37  5063.1 1354.89  5063.4 1354.39
  5067.3 1354.89  5089.5 1355.85  5094.9 1358.49  5102.9 1360.09  5135.1 1362.34
  5167.4 1361.75  5296.6 1370.60  5335.0 1377.32  5394.4 1381.73  5413.3 1384.76
  5418.7 1386.84  5473.3 1389.72  5497.0 1393.60  5502.3 1392.44  5511.8 1392.94
#Mann=6,-1,0
  4561.3    0.05       0  4598.4    0.12       0  4727.5    0.05       0
  5063.1    0.03       0  5067.3    0.05       0  5473.3    0.12       0
Bank Sta=5063.1,5067.3
Exp/Cntr=0.3,0.1

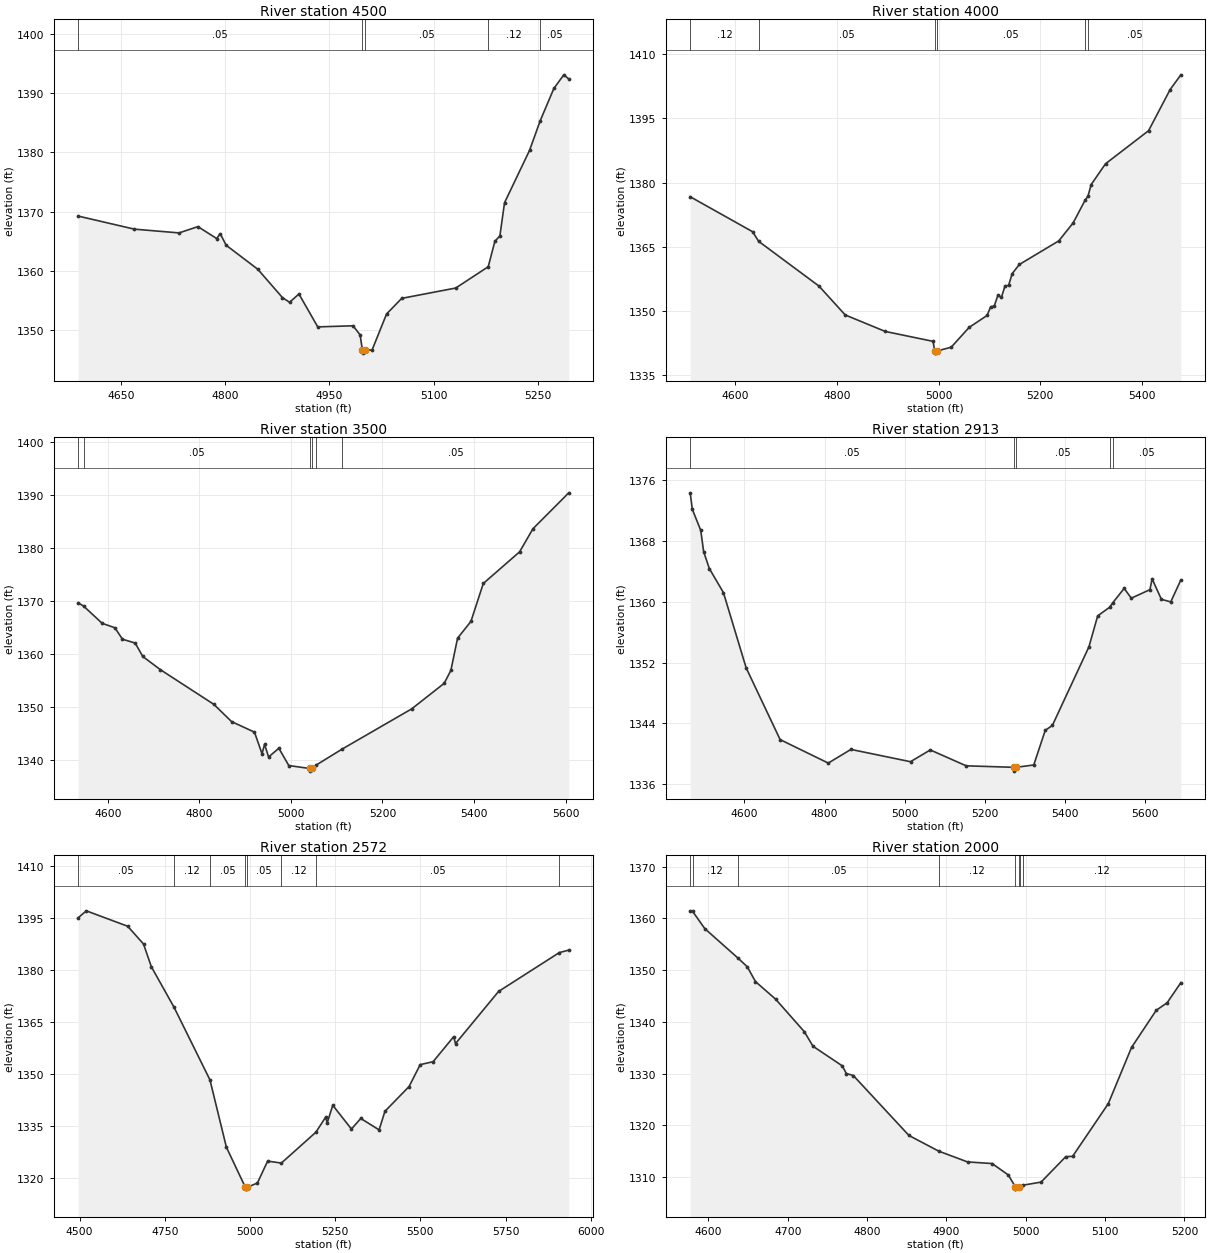
Type RM Length L Ch R = 1,4500,500,500,500
BEGIN DESCRIPTION:
SANFERNANDO054 9.0
END DESCRIPTION:
XS GIS Cut Line= 3
      2792555.69     10291803.08      2792627.31     10291397.35
      2792405.68     10291203.11
#Sta/Elev= 30
  4588.0 1369.24  4669.2 1367.03  4733.5 1366.40  4760.6 1367.46  4787.6 1365.45
  4792.7 1366.28  4801.2 1364.33  4846.9 1360.27  4882.4 1355.49  4892.6 1354.71
  4906.1 1356.10  4933.2 1350.56  4984.0 1350.75  4994.2 1349.22  4997.5 1346.64
  4997.8 1346.14  5001.7 1346.64  5011.4 1346.66  5032.3 1352.74  5054.1 1355.37
  5131.9 1357.11  5178.7 1360.70  5188.3 1364.99  5195.5 1365.89  5202.2 1371.49
  5238.2 1380.30  5253.6 1385.31  5273.3 1390.76  5287.6 1393.04  5294.7 1392.34
#Mann=5,-1,0
  4588.0    0.05       0  4997.5    0.05       0  5001.7    0.05       0
  5178.7    0.12       0  5253.6    0.05       0
Bank Sta=4997.5,5001.7
Exp/Cntr=0.3,0.1

Type RM Length L Ch R = 1,4000,500,500,500
BEGIN DESCRIPTION:
SANFERNANDO054 8.0
END DESCRIPTION:
XS GIS Cut Line= 3
      2793355.69     10291653.12      2793094.83     10291239.28
      2792755.70     10290903.13
#Sta/Elev= 30
  4510.8 1376.69  4633.8 1368.52  4645.6 1366.29  4764.5 1355.84  4816.2 1349.10
  4895.1 1345.25  4989.3 1342.94  4992.5 1340.69  4992.8 1340.19  4997.0 1340.69
  5025.0 1341.57  5060.3 1346.19  5095.7 1348.98  5102.7 1351.00  5109.8 1351.18
  5116.9 1353.66  5124.0 1353.23  5131.0 1355.86  5138.1 1356.00  5145.2 1358.76
  5159.3 1360.88  5237.1 1366.40  5265.4 1370.61  5288.6 1375.84  5294.5 1376.83
  5300.7 1379.52  5329.0 1384.38  5413.9 1392.11  5456.3 1401.70  5477.5 1405.14
#Mann=6,-1,0
  4510.8    0.12       0  4645.6    0.05       0  4992.5    0.05       0
  4997.0    0.05       0  5288.6    0.12       0  5294.5    0.05       0
Bank Sta=4992.5,4997
Exp/Cntr=0.3,0.1

Type RM Length L Ch R = 1,3500,587,587,587
BEGIN DESCRIPTION:
SANFERNANDO054 7.0
END DESCRIPTION:
XS GIS Cut Line= 3
      2793355.68     10291553.12      2793568.35     10291139.72
      2793205.68     10290653.10
#Sta/Elev= 30
  4535.1 1369.69  4547.2 1369.06  4587.7 1365.81  4615.5 1364.97  4632.1 1362.81
  4659.9 1362.08  4676.4 1359.55  4715.0 1357.05  4831.7 1350.51  4870.4 1347.25
  4920.4 1345.26  4936.9 1341.18  4942.5 1342.98  4951.2 1340.57  4973.7 1342.22
  4995.3 1338.96  5040.6 1338.40  5040.9 1337.90  5045.1 1338.40  5055.1 1339.04
  5112.6 1342.10  5263.9 1349.66  5334.8 1354.48  5349.4 1356.92  5364.0 1363.00
  5393.2 1366.17  5420.2 1373.33  5499.5 1379.31  5528.7 1383.67  5606.9 1390.45
#Mann=6,-1,0
  4535.1    0.12       0  4547.2    0.05       0  5040.6    0.05       0
  5045.1    0.05       0  5055.1    0.12       0  5112.6    0.05       0
Bank Sta=5040.6,5045.1
Exp/Cntr=0.3,0.1

Type RM Length L Ch R = 1,2913,341,341,341
BEGIN DESCRIPTION:
Mapping XS 5a061c02
END DESCRIPTION:
XS GIS Cut Line= 3
      2793465.81     10291960.71      2793943.24     10291461.58
      2794160.24     10290973.33
#Sta/Elev= 30
  4464.6 1374.35  4469.9 1372.18  4491.0 1369.40  4498.2 1366.60  4512.4 1364.38
  4547.6 1361.21  4604.2 1351.32  4689.1 1341.86  4809.3 1338.77  4865.9 1340.57
  5014.6 1338.95  5064.0 1340.50  5153.5 1338.41  5273.4 1338.21  5273.7 1337.71
  5278.1 1338.21  5322.3 1338.52  5351.0 1343.08  5368.8 1343.73  5460.0 1354.07
  5481.9 1358.15  5511.8 1359.29  5519.5 1359.87  5548.0 1361.77  5565.8 1360.48
  5612.3 1361.60  5617.8 1363.02  5641.0 1360.33  5664.3 1359.99  5689.6 1362.89
#Mann=5,-1,0
  4464.6    0.05       0  5273.4    0.05       0  5278.1    0.05       0
  5511.8    0.12       0  5519.5    0.05       0
Bank Sta=5273.4,5278.1
Exp/Cntr=0.3,0.1

Type RM Length L Ch R = 1,2572,572,572,572
BEGIN DESCRIPTION:
Mapping XS 35eb1a5a
END DESCRIPTION:
XS GIS Cut Line= 4
      2793932.37     10292123.51      2794160.25     10291613.49
      2794323.01     10291081.81      2794290.67     10290758.37
#Sta/Elev= 30
  4495.5 1395.04  4519.6 1397.08  4641.1 1392.63  4687.5 1387.51  4710.7 1380.90
  4776.9 1369.30  4882.4 1348.32  4930.6 1328.91  4986.4 1317.30  4986.8 1316.80
  4991.2 1317.30  5021.7 1318.57  5051.6 1324.88  5092.0 1324.32  5193.4 1333.23
  5221.5 1337.51  5226.7 1336.00  5242.8 1340.98  5297.5 1334.14  5325.0 1337.19
  5378.7 1333.89  5395.8 1339.25  5466.6 1346.39  5499.3 1352.71  5537.3 1353.57
  5597.6 1360.78  5602.9 1358.78  5729.2 1373.82  5907.4 1385.03  5935.2 1385.75
#Mann=8,-1,0
  4495.5    0.05       0  4776.9    0.12       0  4882.4    0.05       0
  4986.4    0.03       0  4991.2    0.05       0  5092.0    0.12       0
  5193.4    0.05       0  5907.4    0.12       0
Bank Sta=4986.4,4991.2
Exp/Cntr=0.3,0.1

Type RM Length L Ch R = 1,2000,500,500,500
BEGIN DESCRIPTION:
SANFERNANDO054 4.0
END DESCRIPTION:
XS GIS Cut Line= 3
      2794655.68     10291703.10      2794557.13     10291291.74
      2794505.69     10291103.13
#Sta/Elev= 30
  4577.0 1361.48  4580.0 1361.39  4595.4 1358.04  4637.4 1352.32  4649.0 1350.65
  4659.3 1347.79  4684.6 1344.41  4720.9 1338.10  4731.8 1335.29  4768.7 1331.50
  4773.8 1330.02  4782.6 1329.63  4852.7 1318.04  4890.2 1315.01  4926.6 1312.92
  4957.5 1312.61  4978.0 1310.40  4986.6 1308.16  4987.0 1307.66  4991.5 1308.16
  4992.3 1308.20  4996.4 1308.42  5019.3 1309.02  5050.4 1313.94  5059.0 1314.00
  5104.0 1324.19  5133.3 1335.06  5164.4 1342.24  5178.2 1343.70  5195.5 1347.60
#Mann=8,-1,0
  4577.0    0.05       0  4580.0    0.12       0  4637.4    0.05       0
  4890.2    0.12       0  4986.6    0.07       0  4991.5    0.12       0
  4992.3    0.05       0  4996.4    0.12       0
Bank Sta=4986.6,4991.5
Exp/Cntr=0.3,0.1