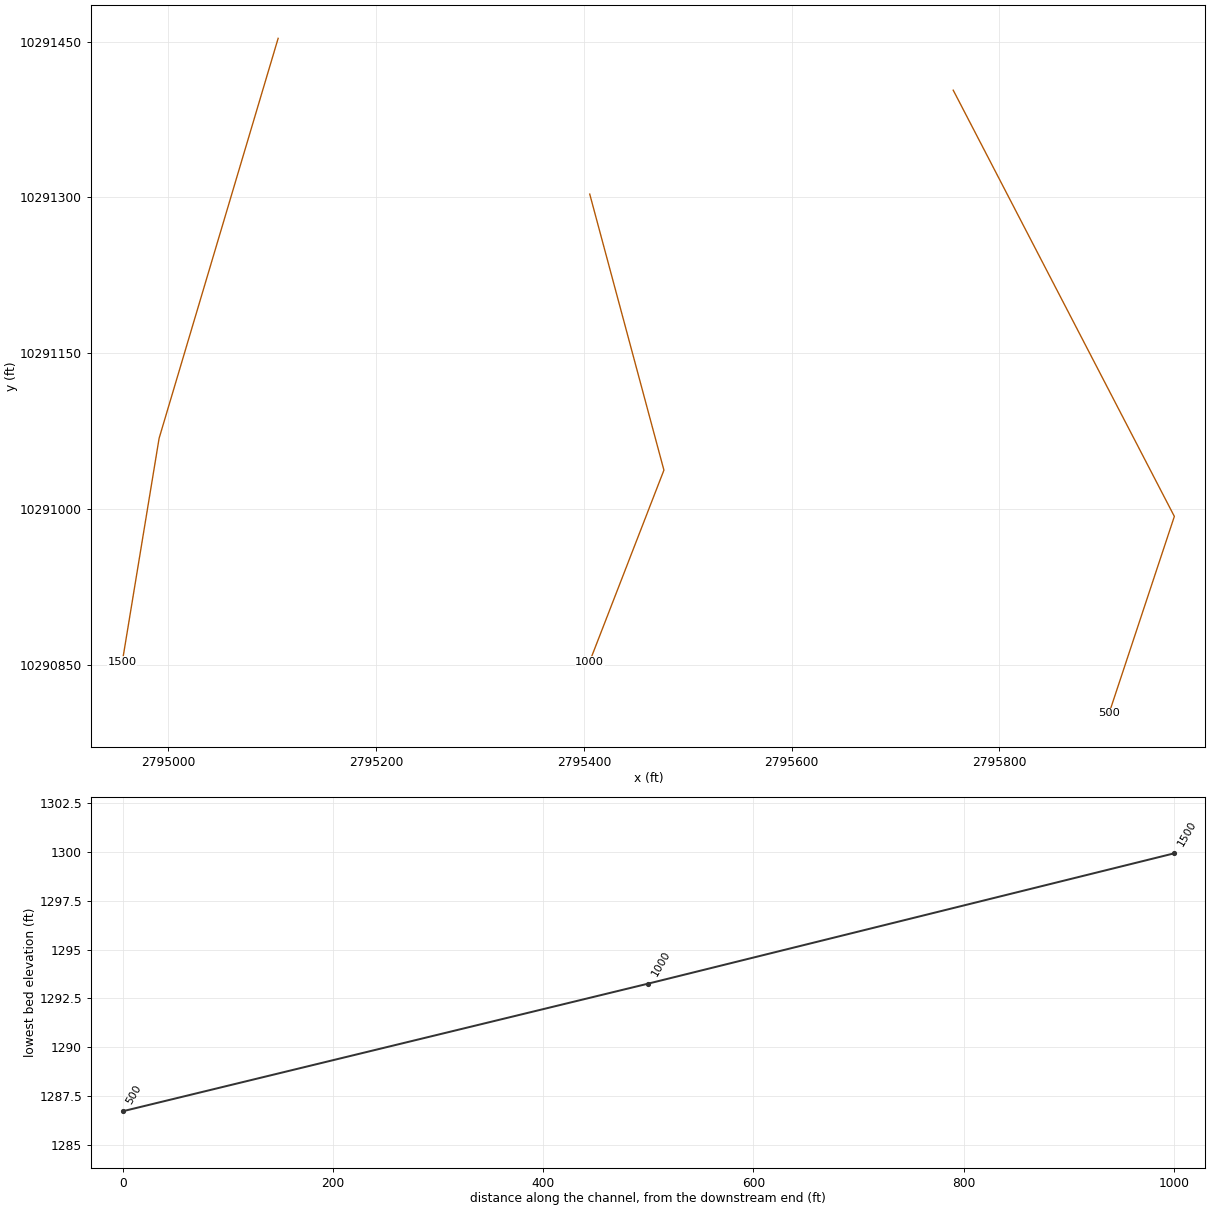
HEC-RAS study SANFERNANDO054.prj: SANFERNANDO054 Base Level Engineering

--- SANFERNANDO054.g01 (geometry) --- (continued)

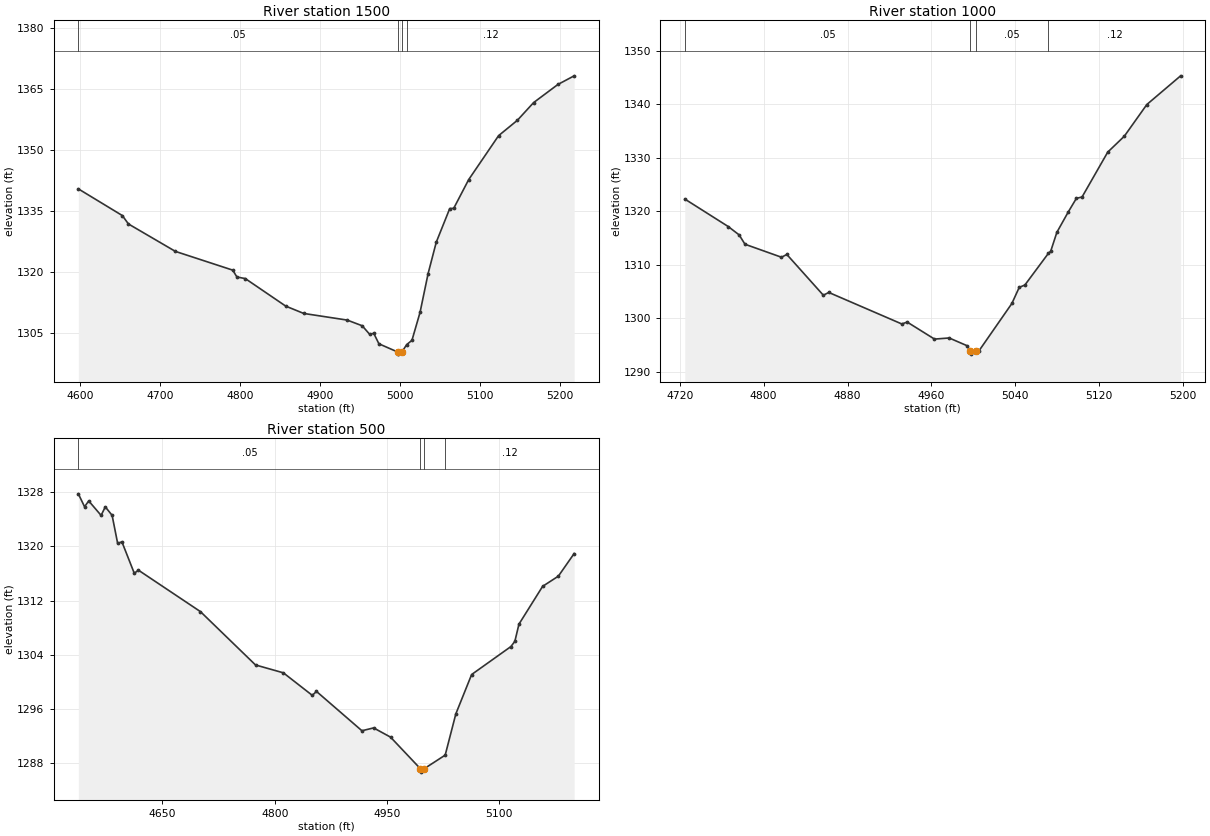
Type RM Length L Ch R = 1,1500,500,500,500
BEGIN DESCRIPTION:
SANFERNANDO054 3.0
END DESCRIPTION:
XS GIS Cut Line= 3
      2795105.67     10291453.08      2794991.06     10291067.97
      2794955.68     10290853.07
#Sta/Elev= 30
  4598.2 1340.52  4653.2 1333.96  4660.8 1331.90  4719.5 1325.16  4791.1 1320.56
  4796.4 1318.87  4806.8 1318.49  4857.4 1311.72  4879.9 1309.92  4934.2 1308.29
  4952.9 1306.90  4962.2 1304.81  4967.4 1305.03  4973.8 1302.47  4997.5 1300.43
  4997.8 1299.93  5002.4 1300.43  5008.6 1302.28  5015.1 1303.32  5025.2 1310.17
  5035.3 1319.72  5045.5 1327.43  5062.3 1335.67  5067.3 1335.74  5086.0 1342.79
  5123.4 1353.59  5146.8 1357.35  5167.1 1361.70  5197.5 1366.16  5217.8 1368.28
#Mann=4,-1,0
  4598.2    0.05       0  4997.5    0.05       0  5002.4    0.05       0
  5008.6    0.12       0
Bank Sta=4997.5,5002.4
Exp/Cntr=0.3,0.1

Type RM Length L Ch R = 1,1000,500,500,500
BEGIN DESCRIPTION:
SANFERNANDO054 2.0
END DESCRIPTION:
XS GIS Cut Line= 3
      2795405.69     10291303.09      2795477.11     10291037.32
      2795405.67     10290853.08
#Sta/Elev= 30
  4724.8 1322.25  4766.2 1317.11  4776.6 1315.55  4782.2 1313.80  4817.0 1311.37
  4822.1 1311.89  4856.9 1304.27  4862.1 1304.79  4931.7 1298.90  4936.9 1299.25
  4962.9 1296.07  4976.9 1296.28  4994.0 1294.83  4997.1 1293.76  4997.5 1293.26
  5002.1 1293.76  5004.9 1293.76  5036.7 1302.73  5043.7 1305.74  5049.1 1306.18
  5071.4 1312.07  5073.7 1312.48  5079.6 1316.03  5090.3 1319.78  5098.2 1322.38
  5103.6 1322.63  5128.1 1331.02  5143.9 1333.99  5165.4 1339.92  5197.6 1345.28
#Mann=4,-1,0
  4724.8    0.05       0  4997.1    0.05       0  5002.1    0.05       0
  5071.4    0.12       0
Bank Sta=4997.1,5002.1
Exp/Cntr=0.3,0.1

Type RM Length L Ch R = 1,500,0,0,0
BEGIN DESCRIPTION:
SANFERNANDO054 1.0
END DESCRIPTION:
XS GIS Cut Line= 3
      2795755.67     10291403.15      2795968.57     10290992.79
      2795905.69     10290803.14
#Sta/Elev= 30
  4537.7 1327.75  4546.0 1325.85  4551.6 1326.70  4568.1 1324.57  4573.7 1325.83
  4582.8 1324.58  4590.2 1320.45  4595.9 1320.67  4612.4 1316.04  4618.0 1316.49
  4700.8 1310.38  4774.3 1302.52  4811.5 1301.36  4850.1 1298.04  4855.7 1298.62
  4916.4 1292.82  4932.0 1293.24  4954.6 1291.88  4994.5 1287.22  4994.9 1286.72
  4999.5 1287.22  5027.6 1289.23  5041.8 1295.31  5062.9 1301.11  5115.3 1305.23
  5120.6 1306.00  5126.1 1308.54  5157.7 1314.11  5178.7 1315.61  5199.8 1318.95
#Mann=4,-1,0
  4537.7    0.05       0  4994.5    0.05       0  4999.5    0.05       0
  5027.6    0.12       0
Bank Sta=4994.5,4999.5
Exp/Cntr=0.3,0.1

Chan Stop Cuts=-1