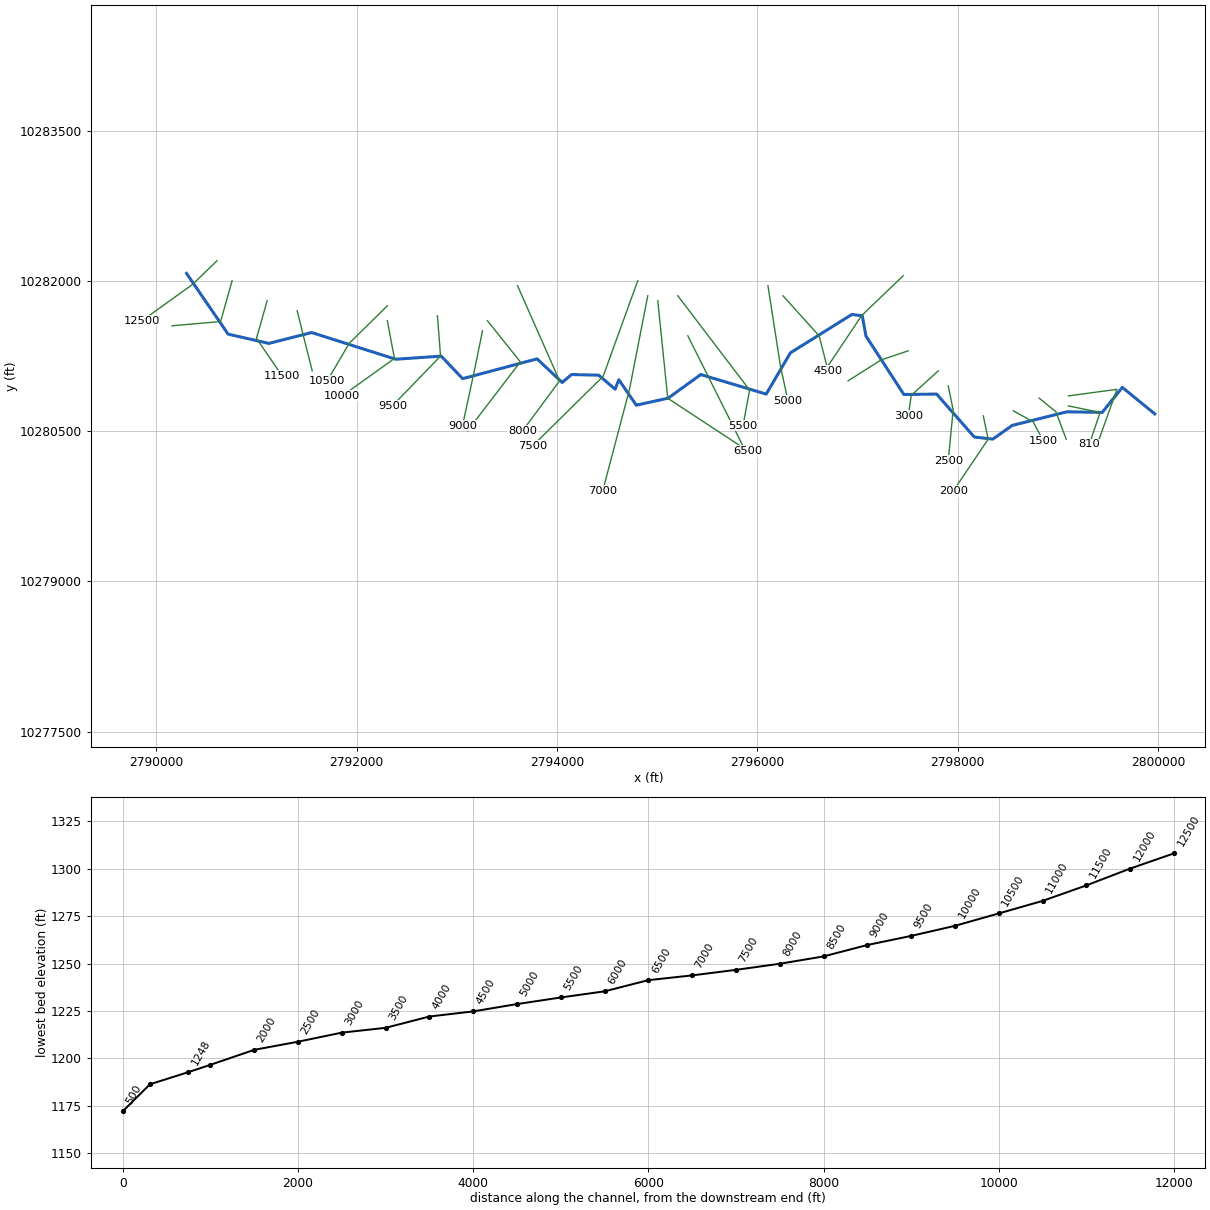
--- SANFERNANDO056.prj (project) ---

Proj Title=SANFERNANDO056 Base Level Engineering
Current Plan=p01
Default Exp/Contr=0.3,0.1
English Units
Geom File=g01
Flow File=f01
Plan File=p01
BEGIN DESCRIPTION:
SANFERNANDO056
END DESCRIPTION:

--- SANFERNANDO056.p01 (plan) ---

Plan Title=Multiple Run
Short Identifier=Multiple
Geom File=g01
Flow File=f01
Subcritical Flow
K Sum by GR= 0
Std Step Tol= 0.01
Critical Tol= 0.01
Num of Std Step Trials= 20
Max Error Tol= 0.3
Flow Tol Ratio= 0.001
Split Flow NTrial= 30
Split Flow Tol= 0.02
Split Flow Ratio= 0.02
Log Output Level= 0
Friction Slope Method= 1
Unsteady Friction Slope Method= 2
Unsteady Bridges Friction Slope Method= 1
Parabolic Critical Depth
Global Vel Dist=  1 , 1 , 1
Global Log Level= 0
CheckData=True
Encroach Param= -1, 0, 0, 0
BEGIN DESCRIPTION:
Multiple Run
END DESCRIPTION:

--- SANFERNANDO056.f01 (steady flow) ---

Flow Title=Multiple
Number of Profiles=7
Profile Names=10-year,25-year,50-year,1pct_min,100-year,1pct_plu,500-year
River Rch & RM= SANFERNANDO056,Reach-1,12500
     479     784    1029     646    1377    2934    1900
River Rch & RM= SANFERNANDO056,Reach-1,1248
     509     838    1156     750    1562    3252    2172
Boundary for River Rch & Prof#=SANFERNANDO056,Reach-1,1
Up Type=0
Dn Type=3
Dn Slope=0.005
Boundary for River Rch & Prof#=SANFERNANDO056,Reach-1,2
Up Type=0
Dn Type=3
Dn Slope=0.005
Boundary for River Rch & Prof#=SANFERNANDO056,Reach-1,3
Up Type=0
Dn Type=3
Dn Slope=0.005
Boundary for River Rch & Prof#=SANFERNANDO056,Reach-1,4
Up Type=0
Dn Type=3
Dn Slope=0.005
Boundary for River Rch & Prof#=SANFERNANDO056,Reach-1,5
Up Type=0
Dn Type=3
Dn Slope=0.005
Boundary for River Rch & Prof#=SANFERNANDO056,Reach-1,6
Up Type=0
Dn Type=3
Dn Slope=0.005
Boundary for River Rch & Prof#=SANFERNANDO056,Reach-1,7
Up Type=0
Dn Type=3
Dn Slope=0.005

--- SANFERNANDO056.g01 (geometry) ---

Geom Title=Existing Conditions

River Reach=SANFERNANDO056,Reach-1
Reach XY= 30
      2790300.75     10282077.00      2790715.75     10281470.00
      2791123.00     10281377.00      2791549.50     10281486.00
      2792389.00     10281219.00      2792843.25     10281250.00
      2793057.75     10281025.00      2793800.50     10281223.00
      2794051.25     10280987.00      2794144.25     10281066.00
      2794415.25     10281060.00      2794580.00     10280920.00
      2794616.50     10281015.00      2794791.00     10280760.00
      2795108.75     10280830.00      2795435.25     10281066.00
      2796088.00     10280871.00      2796329.75     10281283.00
      2796943.00     10281666.00      2797047.25     10281653.00
      2797083.75     10281451.00      2797462.50     10280867.00
      2797789.50     10280871.00      2798165.75     10280442.00
      2798350.75     10280421.00      2798544.50     10280558.00
      2799091.50     10280694.00      2799442.75     10280688.00
      2799643.25     10280938.00      2799967.50     10280673.00

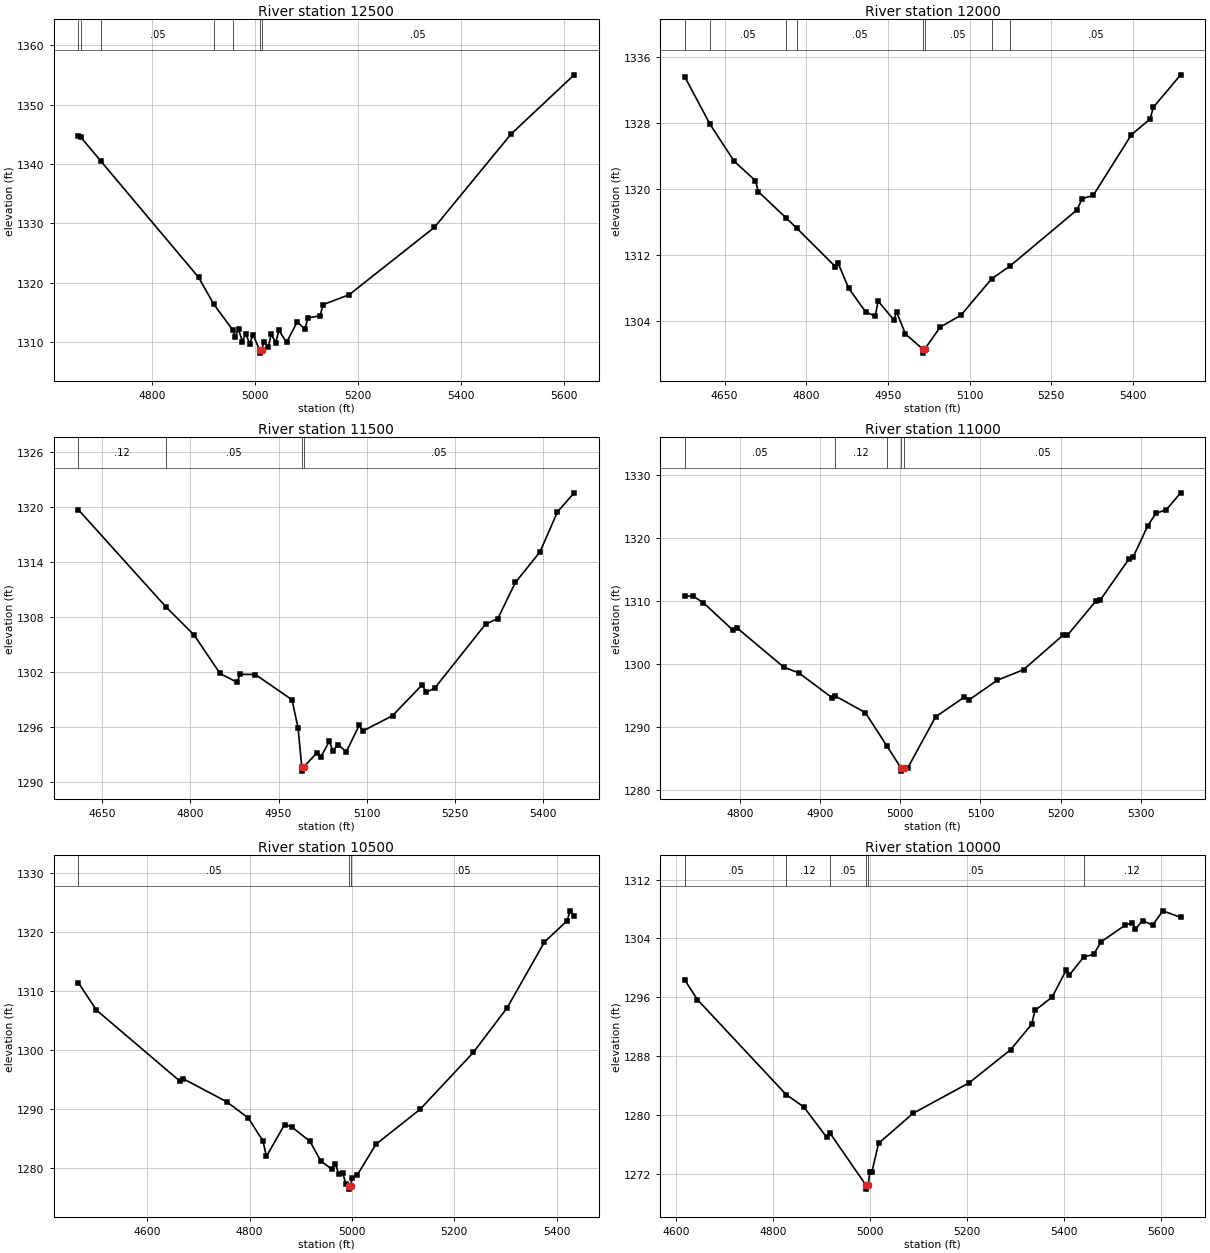
Type RM Length L Ch R = 1,12500,500,500,500
BEGIN DESCRIPTION:
SANFERNANDO056 25.0
END DESCRIPTION:
XS GIS Cut Line= 3
      2790605.65     10282203.08      2790358.42     10281964.76
      2789855.68     10281603.11
#Sta/Elev= 30
  4656.6 1344.69  4660.9 1344.59  4700.5 1340.47  4890.0 1320.90  4919.8 1316.33
  4956.1 1312.06  4960.8 1310.85  4967.7 1312.14  4974.9 1310.06  4981.9 1311.41
  4989.1 1309.68  4996.0 1311.22  5008.5 1308.61  5008.7 1308.11  5012.5 1308.61
  5016.6 1309.95  5025.2 1309.17  5031.3 1311.29  5039.9 1309.87  5046.1 1311.96
  5060.8 1309.91  5081.7 1313.40  5096.4 1312.16  5102.5 1314.05  5125.8 1314.40
  5132.0 1316.30  5182.3 1317.95  5348.0 1329.33  5496.6 1345.04  5619.3 1355.05
#Mann=7,-1,0
  4656.6    0.05       0  4660.9    0.12       0  4700.5    0.05       0
  4919.8    0.12       0  4956.1    0.05       0  5008.5    0.05       0
  5012.5    0.05       0
Bank Sta=5008.5,5012.5
Exp/Cntr=0.3,0.1

Type RM Length L Ch R = 1,12000,500,500,500
BEGIN DESCRIPTION:
SANFERNANDO056 24.0
END DESCRIPTION:
XS GIS Cut Line= 3
      2790755.69     10282003.13      2790641.36     10281595.77
      2790155.73     10281553.12
#Sta/Elev= 30
  4576.9 1333.64  4623.3 1327.88  4667.3 1323.42  4706.6 1321.04  4711.9 1319.71
  4762.7 1316.53  4782.7 1315.26  4853.3 1310.61  4858.5 1311.00  4878.1 1307.96
  4909.3 1305.08  4926.7 1304.60  4931.9 1306.42  4960.8 1304.14  4965.9 1305.10
  4982.0 1302.44  5013.7 1300.60  5014.0 1300.10  5017.7 1300.60  5045.8 1303.25
  5084.3 1304.72  5140.2 1309.11  5174.8 1310.71  5296.8 1317.47  5306.8 1318.86
  5326.9 1319.25  5397.2 1326.62  5431.4 1328.52  5437.4 1329.95  5487.5 1333.89
#Mann=8,-1,0
  4576.9    0.12       0  4623.3    0.05       0  4762.7    0.12       0
  4782.7    0.05       0  5013.7    0.05       0  5017.7    0.05       0
  5140.2    0.12       0  5174.8    0.05       0
Bank Sta=5013.7,5017.7
Exp/Cntr=0.3,0.1

Type RM Length L Ch R = 1,11500,500,500,500
BEGIN DESCRIPTION:
SANFERNANDO056 23.0
END DESCRIPTION:
XS GIS Cut Line= 3
      2791105.69     10281803.13      2790999.18     10281427.02
      2791255.66     10281053.14
#Sta/Elev= 30
  4609.1 1319.70  4758.3 1309.11  4806.2 1306.04  4850.5 1301.85  4879.3 1300.89
  4884.5 1301.76  4910.5 1301.74  4972.9 1298.99  4983.3 1295.91  4989.5 1291.71
  4989.7 1291.21  4993.5 1291.71  5015.6 1293.22  5021.6 1292.70  5036.5 1294.46
  5042.6 1293.44  5051.4 1294.09  5065.4 1293.32  5087.3 1296.20  5093.4 1295.58
  5144.1 1297.25  5194.9 1300.64  5201.0 1299.78  5215.9 1300.25  5302.5 1307.22
  5323.5 1307.84  5353.3 1311.77  5395.2 1315.10  5425.0 1319.46  5453.4 1321.54
#Mann=4,-1,0
  4609.1    0.12       0  4758.3    0.05       0  4989.5    0.05       0
  4993.5    0.05       0
Bank Sta=4989.5,4993.5
Exp/Cntr=0.3,0.1

Type RM Length L Ch R = 1,11000,500,500,500
BEGIN DESCRIPTION:
SANFERNANDO056 22.0
END DESCRIPTION:
XS GIS Cut Line= 3
      2791405.69     10281703.07      2791470.31     10281442.16
      2791555.68     10281103.14
#Sta/Elev= 30
  4731.2 1310.83  4741.5 1310.84  4754.4 1309.78  4790.7 1305.49  4795.8 1305.84
  4854.8 1299.53  4873.5 1298.63  4914.9 1294.69  4918.7 1294.98  4956.3 1292.33
  4983.1 1287.06  5000.9 1283.53  5001.1 1283.03  5004.9 1283.53  5009.3 1283.55
  5044.0 1291.65  5079.9 1294.79  5085.1 1294.30  5121.0 1297.47  5153.7 1299.15
  5203.2 1304.66  5208.4 1304.62  5244.3 1310.11  5249.5 1310.23  5285.4 1316.78
  5290.6 1317.09  5308.4 1321.95  5318.7 1323.99  5331.7 1324.54  5349.6 1327.24
#Mann=5,-1,0
  4731.2    0.05       0  4918.7    0.12       0  4983.1    0.05       0
  5000.9    0.05       0  5004.9    0.05       0
Bank Sta=5000.9,5004.9
Exp/Cntr=0.3,0.1

Type RM Length L Ch R = 1,10500,500,500,500
BEGIN DESCRIPTION:
SANFERNANDO056 21.0
END DESCRIPTION:
XS GIS Cut Line= 3
      2792305.66     10281753.09      2791924.88     10281377.98
      2791705.66     10281003.07
#Sta/Elev= 30
  4465.5 1311.39  4500.8 1306.75  4663.4 1294.75  4670.5 1295.12  4755.4 1291.22
  4797.8 1288.46  4826.1 1284.61  4833.1 1281.98  4868.5 1287.37  4882.7 1286.94
  4918.0 1284.53  4939.3 1281.19  4960.4 1279.83  4967.6 1280.72  4974.6 1278.92
  4981.7 1279.19  4988.7 1277.24  4993.8 1276.93  4994.1 1276.43  4997.8 1276.93
  4999.9 1278.32  5009.9 1278.74  5047.1 1284.03  5133.1 1289.93  5237.3 1299.57
  5303.3 1307.13  5376.3 1318.27  5420.6 1321.88  5426.4 1323.55  5434.3 1322.66
#Mann=3,-1,0
  4465.5    0.05       0  4993.8    0.05       0  4997.8    0.05       0
Bank Sta=4993.8,4997.8
Exp/Cntr=0.3,0.1

Type RM Length L Ch R = 1,10000,500,500,500
BEGIN DESCRIPTION:
SANFERNANDO056 20.0
END DESCRIPTION:
XS GIS Cut Line= 3
      2792305.69     10281603.08      2792376.70     10281227.02
      2791855.69     10280853.11
#Sta/Elev= 30
  4617.3 1298.34  4643.5 1295.66  4826.6 1282.75  4863.2 1281.06  4910.5 1276.92
  4917.5 1277.47  4991.8 1270.38  4992.1 1269.88  4995.8 1270.38  4999.4 1272.22
  5003.7 1272.22  5017.5 1276.11  5088.7 1280.20  5204.1 1284.33  5290.1 1288.85
  5333.6 1292.32  5340.5 1294.20  5376.1 1296.03  5405.5 1299.76  5411.7 1299.04
  5440.9 1301.45  5462.0 1301.86  5476.8 1303.53  5527.1 1305.82  5541.8 1306.17
  5548.0 1305.26  5562.7 1306.44  5583.6 1305.81  5604.5 1307.76  5641.3 1306.87
#Mann=6,-1,0
  4617.3    0.05       0  4826.6    0.12       0  4917.5    0.05       0
  4991.8    0.05       0  4995.8    0.05       0  5440.9    0.12       0
Bank Sta=4991.8,4995.8
Exp/Cntr=0.3,0.1

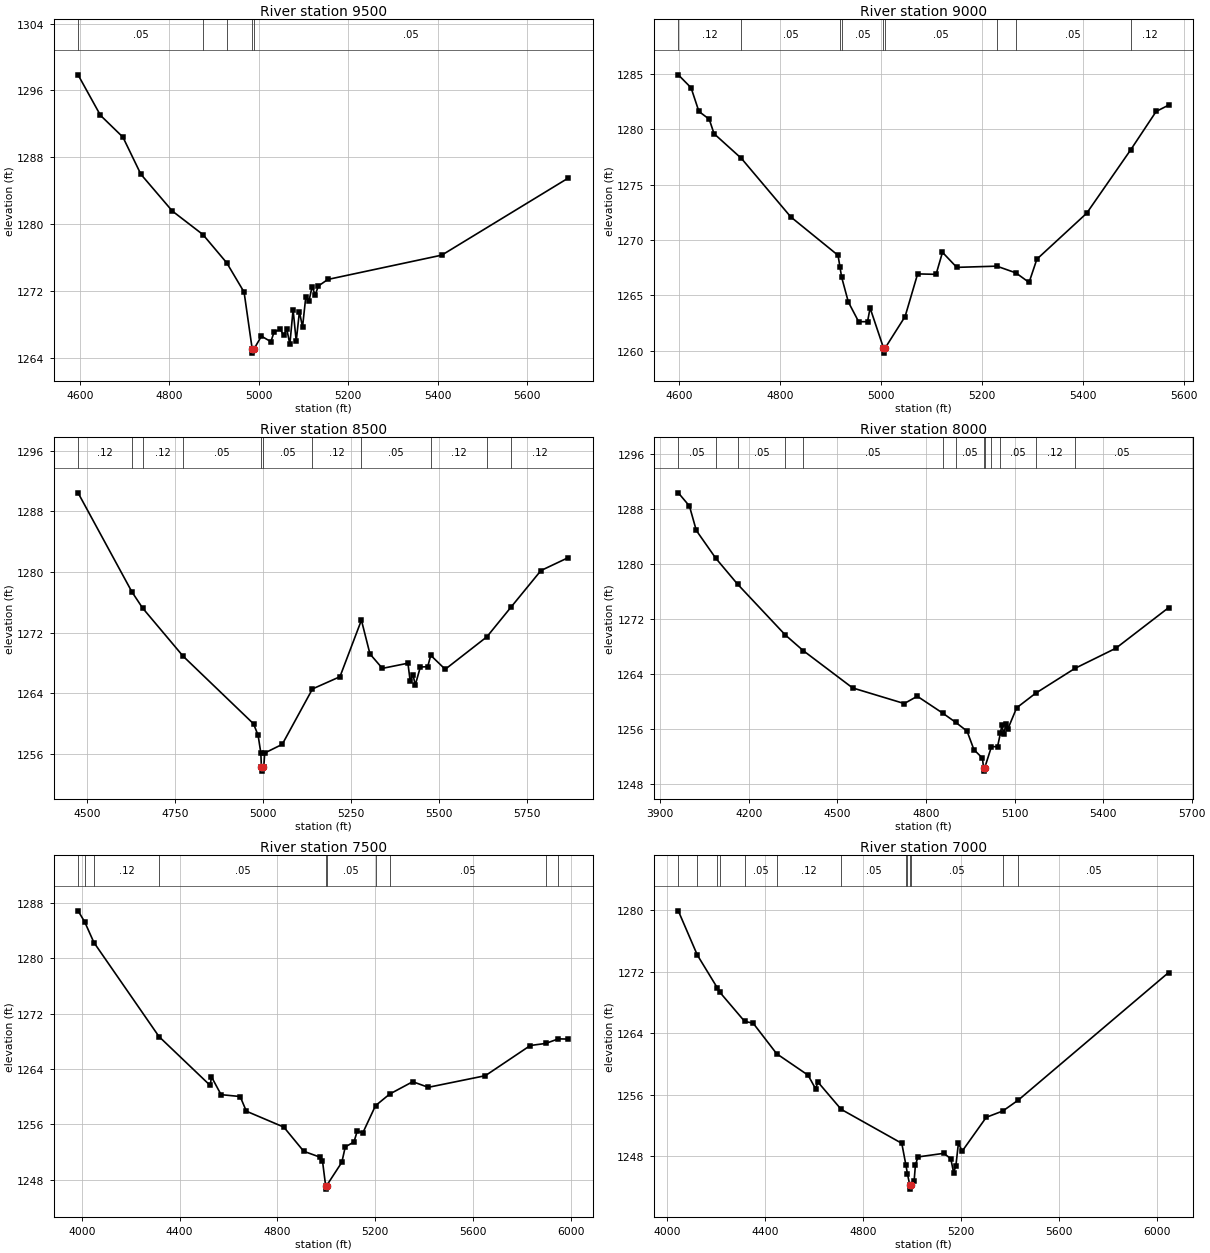
Type RM Length L Ch R = 1,9500,500,500,500
BEGIN DESCRIPTION:
SANFERNANDO056 19.0
END DESCRIPTION:
XS GIS Cut Line= 3
      2792805.68     10281653.11      2792836.87     10281250.62
      2792355.71     10280753.14
#Sta/Elev= 30
  4596.3 1297.87  4646.4 1293.02  4696.6 1290.41  4736.7 1285.97  4806.9 1281.57
  4875.4 1278.75  4928.7 1275.36  4967.4 1271.86  4985.5 1265.06  4985.7 1264.56
  4989.5 1265.06  5006.2 1266.59  5027.3 1265.93  5034.5 1267.10  5048.6 1267.40
  5055.6 1266.69  5062.8 1267.43  5069.7 1265.63  5076.9 1269.76  5083.9 1266.00
  5091.1 1269.54  5098.0 1267.67  5105.2 1271.24  5112.2 1270.74  5119.4 1272.52
  5126.3 1271.52  5133.5 1272.60  5154.6 1273.38  5409.3 1276.29  5692.1 1285.52
#Mann=5,-1,0
  4596.3    0.05       0  4875.4    0.12       0  4928.7    0.05       0
  4985.5    0.05       0  4989.5    0.05       0
Bank Sta=4985.5,4989.5
Exp/Cntr=0.3,0.1

Type RM Length L Ch R = 1,9000,500,500,500
BEGIN DESCRIPTION:
SANFERNANDO056 18.0
END DESCRIPTION:
XS GIS Cut Line= 3
      2793255.68     10281503.07      2793175.92     10281110.18
      2793055.68     10280553.11
#Sta/Elev= 30
  4599.1 1284.92  4624.4 1283.75  4639.9 1281.61  4660.3 1280.91  4669.9 1279.60
  4724.0 1277.37  4821.8 1272.08  4915.4 1268.61  4919.3 1267.53  4922.5 1266.64
  4935.8 1264.39  4956.2 1262.61  4973.8 1262.61  4978.9 1263.85  5005.2 1260.27
  5005.5 1259.77  5009.2 1260.27  5048.2 1263.08  5073.0 1266.93  5109.5 1266.89
  5122.2 1268.88  5150.5 1267.52  5229.8 1267.63  5267.6 1267.02  5293.7 1266.16
  5309.1 1268.26  5407.7 1272.41  5494.7 1278.13  5545.3 1281.61  5569.9 1282.18
#Mann=9,-1,0
  4599.1    0.12       0  4724.0    0.05       0  4919.3    0.12       0
  4922.5    0.05       0  5005.2    0.05       0  5009.2    0.05       0
  5229.8    0.12       0  5267.6    0.05       0  5494.7    0.12       0
Bank Sta=5005.2,5009.2
Exp/Cntr=0.3,0.1

Type RM Length L Ch R = 1,8500,500,500,500
BEGIN DESCRIPTION:
SANFERNANDO056 17.0
END DESCRIPTION:
XS GIS Cut Line= 3
      2793305.68     10281603.11      2793633.55     10281192.44
      2793105.70     10280503.13
#Sta/Elev= 30
  4474.5 1290.44  4627.7 1277.37  4658.1 1275.24  4772.9 1268.91  4973.3 1259.98
  4986.3 1258.47  4994.1 1256.13  4995.7 1254.24  4996.0 1253.74  4999.7 1254.24
  5002.4 1254.24  5005.1 1256.13  5054.9 1257.27  5140.9 1264.58  5219.0 1266.19
  5280.0 1273.65  5304.3 1269.19  5339.6 1267.29  5412.2 1267.97  5418.5 1265.66
  5426.7 1266.46  5433.0 1265.08  5447.5 1267.47  5468.4 1267.51  5477.1 1269.01
  5518.2 1267.17  5636.6 1271.45  5705.5 1275.38  5790.3 1280.19  5868.2 1281.90
#Mann=11,-1,0
  4474.5    0.12       0  4627.7    0.05       0  4658.1    0.12       0
  4772.9    0.05       0  4995.7    0.05       0  4999.7    0.05       0
  5140.9    0.12       0  5280.0    0.05       0  5477.1    0.12       0
  5636.6    0.05       0  5705.5    0.12       0
Bank Sta=4995.7,4999.7
Exp/Cntr=0.3,0.1

Type RM Length L Ch R = 1,8000,500,500,500
BEGIN DESCRIPTION:
SANFERNANDO056 16.0
END DESCRIPTION:
XS GIS Cut Line= 3
      2793605.67     10281953.15      2794025.44     10281003.05
      2793655.69     10280503.12
#Sta/Elev= 30
  3961.3 1290.31  3999.0 1288.39  4022.3 1284.84  4088.1 1280.81  4162.0 1277.04
  4323.6 1269.66  4384.1 1267.39  4551.7 1261.96  4726.6 1259.69  4770.7 1260.75
  4856.4 1258.31  4901.1 1256.95  4939.3 1255.68  4962.6 1252.98  4991.3 1251.77
  4995.2 1250.37  4995.5 1249.87  4999.2 1250.37  5022.0 1253.44  5042.5 1253.41
  5052.3 1255.40  5057.2 1256.54  5063.4 1255.32  5071.8 1256.75  5078.0 1256.05
  5107.3 1259.07  5171.3 1261.18  5304.7 1264.80  5443.4 1267.73  5621.8 1273.62
#Mann=13,-1,0
  3961.3    0.05       0  4088.1    0.12       0  4162.0    0.05       0
  4323.6    0.12       0  4384.1    0.05       0  4856.4    0.12       0
  4901.1    0.05       0  4995.2    0.05       0  4999.2    0.05       0
  5022.0    0.12       0  5052.3    0.05       0  5171.3    0.12       0
  5304.7    0.05       0
Bank Sta=4995.2,4999.2
Exp/Cntr=0.3,0.1

Type RM Length L Ch R = 1,7500,500,500,500
BEGIN DESCRIPTION:
SANFERNANDO056 15.0
END DESCRIPTION:
XS GIS Cut Line= 3
      2794805.70     10282003.16      2794460.30     10281048.63
      2793755.66     10280353.09
#Sta/Elev= 30
  3984.9 1286.86  4011.8 1285.28  4049.8 1282.28  4316.0 1268.69  4525.3 1261.63
  4530.6 1262.87  4569.8 1260.30  4647.9 1260.03  4673.2 1257.91  4826.5 1255.61
  4907.8 1252.12  4974.4 1251.27  4984.6 1250.73  4997.4 1247.15  4997.7 1246.65
  5001.4 1247.15  5063.7 1250.53  5077.8 1252.76  5113.2 1253.45  5127.4 1255.12
  5148.6 1254.71  5201.5 1258.71  5259.6 1260.39  5353.7 1262.17  5417.3 1261.36
  5650.7 1263.04  5834.5 1267.40  5897.3 1267.70  5949.4 1268.36  5990.1 1268.33
#Mann=10,-1,0
  3984.9    0.12       0  4011.8    0.05       0  4049.8    0.12       0
  4316.0    0.05       0  4997.4    0.05       0  5001.4    0.05       0
  5201.5    0.12       0  5259.6    0.05       0  5897.3    0.12       0
  5949.4    0.05       0
Bank Sta=4997.4,5001.4
Exp/Cntr=0.3,0.1

Type RM Length L Ch R = 1,7000,500,500,500
BEGIN DESCRIPTION:
SANFERNANDO056 14.0
END DESCRIPTION:
XS GIS Cut Line= 3
      2794905.69     10281853.15      2794722.76     10280915.74
      2794455.67     10279903.07
#Sta/Elev= 30
  4044.9 1279.89  4122.7 1274.14  4203.6 1269.92  4214.8 1269.30  4315.7 1265.53
  4350.6 1265.29  4446.7 1261.32  4574.8 1258.54  4605.3 1256.79  4615.5 1257.63
  4710.0 1254.10  4957.7 1249.68  4974.6 1246.84  4980.8 1245.71  4990.5 1244.23
  4990.7 1243.73  4994.5 1244.23  5008.0 1244.76  5013.2 1246.81  5023.4 1247.91
  5128.9 1248.38  5157.8 1247.69  5169.2 1245.89  5178.5 1246.72  5188.9 1249.69
  5204.3 1248.66  5302.6 1253.06  5370.2 1253.88  5433.6 1255.30  6047.3 1271.87
#Mann=13,-1,0
  4044.9    0.05       0  4122.7    0.12       0  4203.6    0.05       0
  4214.8    0.12       0  4315.7    0.05       0  4446.7    0.12       0
  4710.0    0.05       0  4974.6    0.12       0  4980.8    0.05       0
  4990.5    0.05       0  4994.5    0.05       0  5370.2    0.12       0
  5433.6    0.05       0
Bank Sta=4990.5,4994.5
Exp/Cntr=0.3,0.1

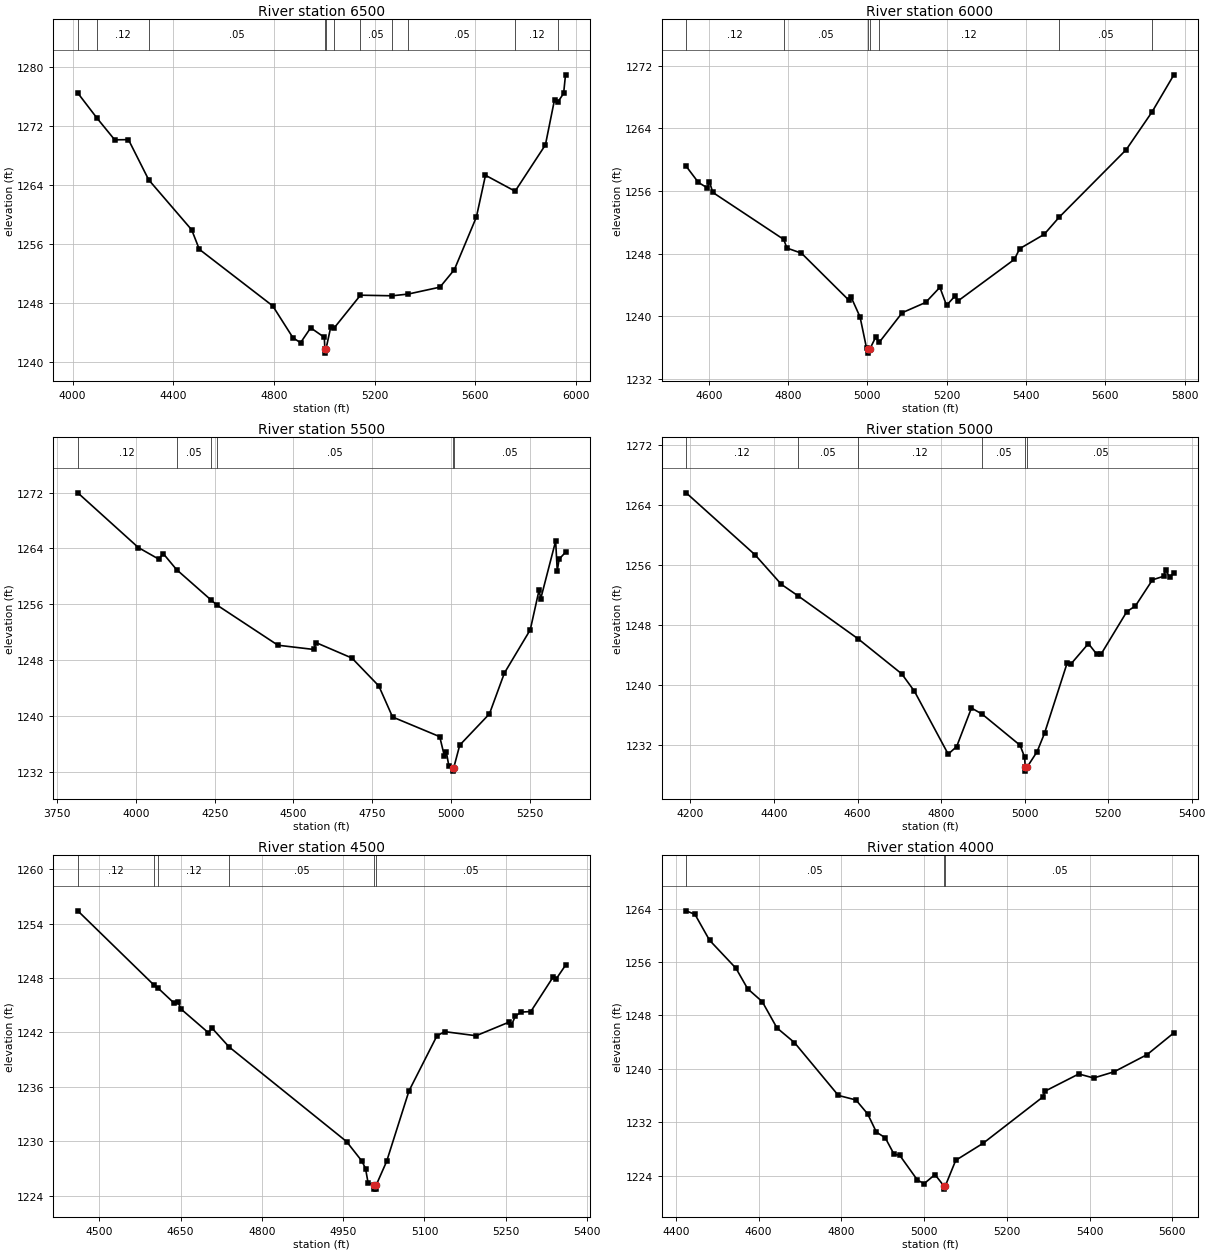
Type RM Length L Ch R = 1,6500,500,500,500
BEGIN DESCRIPTION:
SANFERNANDO056 13.0
END DESCRIPTION:
XS GIS Cut Line= 3
      2795005.68     10281803.15      2795105.30     10280829.23
      2795905.67     10280303.12
#Sta/Elev= 30
  4021.0 1276.45  4097.3 1273.05  4167.6 1270.11  4222.1 1270.14  4302.6 1264.69
  4473.4 1257.91  4503.5 1255.28  4795.1 1247.61  4875.5 1243.29  4905.6 1242.62
  4945.8 1244.64  5000.0 1243.35  5002.2 1241.71  5002.5 1241.21  5006.2 1241.71
  5025.3 1244.71  5038.6 1244.60  5143.5 1249.06  5269.2 1248.98  5332.5 1249.21
  5459.2 1250.15  5516.4 1252.52  5603.8 1259.64  5640.0 1265.31  5757.7 1263.15
  5878.0 1269.43  5914.1 1275.54  5928.6 1275.29  5950.3 1276.41  5957.8 1278.92
#Mann=11,-1,0
  4021.0    0.05       0  4097.3    0.12       0  4302.6    0.05       0
  5002.2    0.05       0  5006.2    0.05       0  5038.6    0.12       0
  5143.5    0.05       0  5269.2    0.12       0  5332.5    0.05       0
  5757.7    0.12       0  5928.6    0.05       0
Bank Sta=5002.2,5006.2
Exp/Cntr=0.3,0.1

Type RM Length L Ch R = 1,6000,500,500,500
BEGIN DESCRIPTION:
SANFERNANDO056 12.0
END DESCRIPTION:
XS GIS Cut Line= 3
      2795305.68     10281453.12      2795510.38     10281044.64
      2795855.66     10280353.15
#Sta/Elev= 30
  4543.1 1259.17  4573.8 1257.11  4596.2 1256.41  4601.8 1257.21  4610.2 1255.83
  4789.0 1249.83  4797.3 1248.72  4833.9 1248.07  4953.7 1242.05  4959.3 1242.43
  4981.6 1239.93  4998.1 1235.91  5002.0 1235.81  5002.2 1235.31  5006.0 1235.81
  5020.8 1237.32  5029.7 1236.67  5087.9 1240.47  5147.0 1241.78  5182.9 1243.71
  5199.7 1241.41  5222.1 1242.66  5227.7 1241.94  5370.6 1247.27  5384.3 1248.65
  5445.8 1250.47  5483.5 1252.65  5652.7 1261.28  5717.7 1266.09  5772.9 1270.84
#Mann=7,-1,0
  4543.1    0.12       0  4789.0    0.05       0  5002.0    0.05       0
  5006.0    0.05       0  5029.7    0.12       0  5483.5    0.05       0
  5717.7    0.12       0
Bank Sta=5002,5006
Exp/Cntr=0.3,0.1

Type RM Length L Ch R = 1,5500,500,500,500
BEGIN DESCRIPTION:
SANFERNANDO056 11.0
END DESCRIPTION:
XS GIS Cut Line= 3
      2795205.71     10281853.07      2795922.79     10280910.41
      2795855.69     10280553.16
#Sta/Elev= 30
  3815.6 1271.97  4007.9 1264.12  4072.3 1262.47  4086.9 1263.25  4128.9 1260.97
  4239.9 1256.55  4256.9 1255.89  4450.8 1250.12  4565.1 1249.51  4571.4 1250.50
  4685.7 1248.28  4771.0 1244.28  4814.6 1239.83  4964.3 1237.01  4978.9 1234.26
  4985.2 1234.83  4993.4 1232.78  5004.9 1232.57  5005.1 1232.07  5008.9 1232.57
  5027.8 1235.80  5122.1 1240.28  5169.5 1246.13  5251.6 1252.33  5279.7 1258.05
  5284.8 1256.77  5332.2 1265.06  5337.3 1260.79  5343.2 1262.46  5363.5 1263.45
#Mann=6,-1,0
  3815.6    0.12       0  4128.9    0.05       0  4239.9    0.12       0
  4256.9    0.05       0  5004.9    0.05       0  5008.9    0.05       0
Bank Sta=5004.9,5008.9
Exp/Cntr=0.3,0.1

Type RM Length L Ch R = 1,5000,500,500,500
BEGIN DESCRIPTION:
SANFERNANDO056 10.0
END DESCRIPTION:
XS GIS Cut Line= 3
      2796105.68     10281953.12      2796230.08     10281152.43
      2796305.68     10280803.11
#Sta/Elev= 30
  4189.7 1265.60  4354.6 1257.36  4417.6 1253.43  4457.1 1251.92  4602.0 1246.16
  4705.8 1241.53  4736.2 1239.22  4817.1 1230.85  4837.4 1231.86  4872.8 1236.98
  4898.2 1236.18  4989.2 1232.03  5000.0 1230.46  5001.6 1229.09  5001.9 1228.59
  5005.6 1229.09  5030.0 1231.18  5047.7 1233.62  5102.1 1243.00  5111.8 1242.89
  5152.8 1245.55  5173.2 1244.11  5183.5 1244.18  5244.9 1249.81  5265.3 1250.55
  5306.2 1254.03  5332.8 1254.50  5337.9 1255.36  5347.2 1254.38  5357.4 1254.98
#Mann=6,-1,0
  4189.7    0.12       0  4457.1    0.05       0  4602.0    0.12       0
  4898.2    0.05       0  5001.6    0.05       0  5005.6    0.05       0
Bank Sta=5001.6,5005.6
Exp/Cntr=0.3,0.1

Type RM Length L Ch R = 1,4500,500,500,500
BEGIN DESCRIPTION:
SANFERNANDO056 9.0
END DESCRIPTION:
XS GIS Cut Line= 3
      2796255.71     10281853.08      2796617.16     10281452.29
      2796705.68     10281103.14
#Sta/Elev= 30
  4460.3 1255.40  4600.8 1247.22  4608.6 1246.87  4637.0 1245.28  4644.5 1245.40
  4651.2 1244.55  4701.3 1241.96  4708.0 1242.47  4739.4 1240.40  4956.1 1229.97
  4984.5 1227.81  4991.2 1226.99  4996.1 1225.35  5007.3 1225.22  5007.6 1224.72
  5011.1 1224.72  5011.3 1225.22  5030.1 1227.77  5071.4 1235.55  5123.0 1241.62
  5137.4 1242.08  5195.2 1241.63  5255.2 1243.11  5260.4 1242.78  5267.4 1243.77
  5277.7 1244.23  5296.2 1244.30  5337.2 1248.09  5342.3 1247.83  5360.2 1249.40
#Mann=6,-1,0
  4460.3    0.12       0  4600.8    0.05       0  4608.6    0.12       0
  4739.4    0.05       0  5007.3    0.05       0  5011.3    0.05       0
Bank Sta=5007.3,5011.3
Exp/Cntr=0.3,0.1

Type RM Length L Ch R = 1,4000,500,500,500
BEGIN DESCRIPTION:
SANFERNANDO056 8.0
END DESCRIPTION:
XS GIS Cut Line= 3
      2797455.72     10282053.14      2797040.96     10281655.04
      2796705.69     10281153.12
#Sta/Elev= 30
  4425.1 1263.66  4446.4 1263.13  4481.6 1259.26  4545.4 1255.07  4573.7 1252.00
  4609.0 1250.07  4644.5 1246.14  4686.9 1243.94  4792.9 1236.04  4835.4 1235.36
  4863.7 1233.27  4884.8 1230.55  4906.1 1229.71  4927.2 1227.27  4941.4 1227.06
  4983.8 1223.39  5000.0 1222.83  5026.4 1224.20  5047.5 1222.52  5047.7 1222.02
  5051.5 1222.52  5076.5 1226.33  5142.6 1228.88  5286.7 1235.79  5292.7 1236.69
  5373.8 1239.25  5409.9 1238.65  5459.3 1239.58  5539.0 1242.15  5603.6 1245.40
#Mann=3,-1,0
  4425.1    0.05       0  5047.5    0.03       0  5051.5    0.05       0
Bank Sta=5047.5,5051.5
Exp/Cntr=0.3,0.1

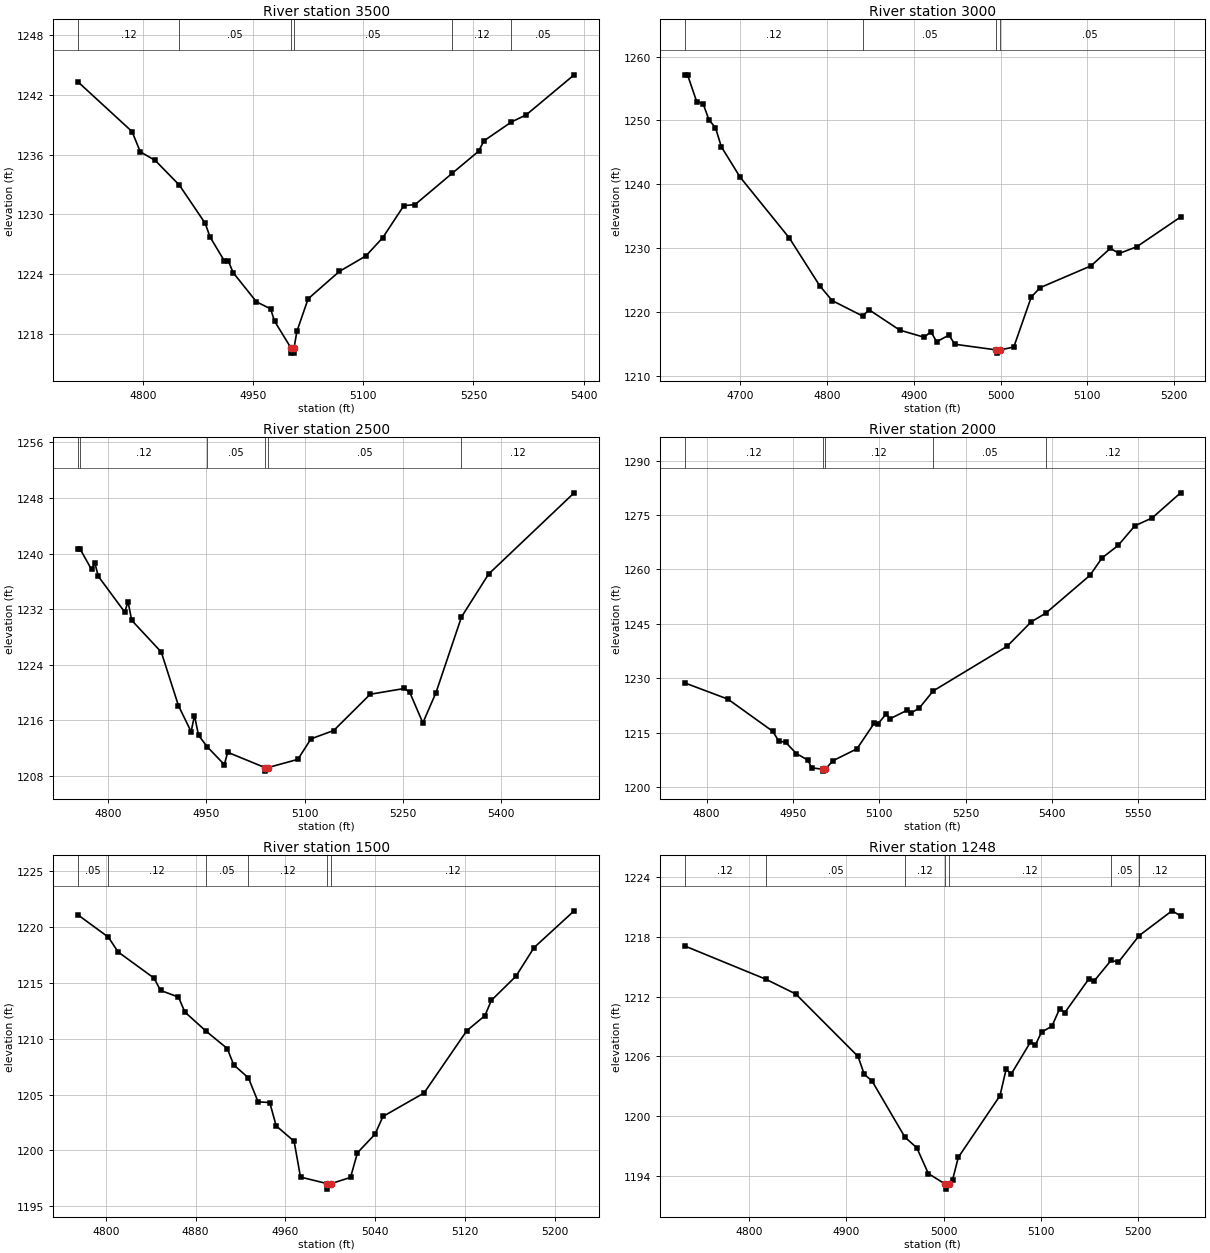
Type RM Length L Ch R = 1,3500,500,500,500
BEGIN DESCRIPTION:
SANFERNANDO056 7.0
END DESCRIPTION:
XS GIS Cut Line= 3
      2797505.70     10281303.12      2797232.47     10281210.83
      2796905.70     10281003.12
#Sta/Elev= 30
  4711.6 1243.30  4785.0 1238.32  4796.1 1236.29  4816.4 1235.43  4849.4 1232.94
  4884.6 1229.10  4891.1 1227.74  4910.8 1225.31  4916.1 1225.31  4922.7 1224.14
  4954.4 1221.21  4973.7 1220.50  4979.0 1219.27  5001.6 1216.55  5001.8 1216.05
  5005.3 1216.05  5005.6 1216.55  5009.5 1218.24  5024.8 1221.51  5067.3 1224.26
  5103.5 1225.82  5126.5 1227.66  5155.2 1230.88  5170.4 1230.98  5220.9 1234.12
  5256.9 1236.34  5264.4 1237.40  5301.8 1239.29  5322.0 1240.01  5387.2 1244.03
#Mann=6,-1,0
  4711.6    0.12       0  4849.4    0.05       0  5001.6    0.05       0
  5005.6    0.05       0  5220.9    0.12       0  5301.8    0.05       0
Bank Sta=5001.6,5005.6
Exp/Cntr=0.3,0.1

Type RM Length L Ch R = 1,3000,500,500,500
BEGIN DESCRIPTION:
SANFERNANDO056 6.0
END DESCRIPTION:
XS GIS Cut Line= 3
      2797805.65     10281103.08      2797536.72     10280858.22
      2797505.69     10280653.15
#Sta/Elev= 30
  4636.3 1257.13  4639.6 1257.13  4650.1 1252.94  4657.5 1252.62  4664.3 1250.05
  4671.7 1248.87  4678.5 1245.86  4700.1 1241.10  4756.9 1231.54  4792.0 1224.03
  4806.2 1221.74  4841.1 1219.33  4848.8 1220.29  4883.9 1217.12  4912.3 1215.99
  4919.7 1216.89  4926.5 1215.30  4940.6 1216.33  4947.4 1214.90  4995.3 1214.01
  4995.6 1213.51  4999.3 1214.01  5015.3 1214.47  5035.4 1222.29  5045.6 1223.77
  5104.2 1227.19  5126.5 1229.94  5136.6 1229.13  5156.9 1230.18  5207.4 1234.85
#Mann=4,-1,0
  4636.3    0.12       0  4841.1    0.05       0  4995.3    0.05       0
  4999.3    0.05       0
Bank Sta=4995.3,4999.3
Exp/Cntr=0.3,0.1

Type RM Length L Ch R = 1,2500,500,500,500
BEGIN DESCRIPTION:
SANFERNANDO056 5.0
END DESCRIPTION:
XS GIS Cut Line= 3
      2797905.68     10280953.13      2797954.41     10280712.52
      2797905.69     10280203.14
#Sta/Elev= 30
  4754.5 1240.70  4757.2 1240.68  4774.8 1237.72  4779.9 1238.65  4785.1 1236.74
  4825.5 1231.59  4830.6 1233.08  4836.1 1230.41  4881.3 1225.84  4907.6 1218.12
  4926.9 1214.39  4932.0 1216.71  4938.2 1213.88  4951.2 1212.25  4977.6 1209.65
  4982.7 1211.43  5039.9 1209.22  5040.1 1208.72  5043.9 1209.22  5089.8 1210.41
  5109.9 1213.36  5144.6 1214.56  5200.3 1219.77  5252.4 1220.60  5260.6 1220.07
  5280.7 1215.65  5300.8 1220.02  5339.7 1230.89  5381.1 1237.05  5511.7 1248.73
#Mann=6,-1,0
  4754.5    0.05       0  4757.2    0.12       0  4951.2    0.05       0
  5039.9    0.05       0  5043.9    0.05       0  5339.7    0.12       0
Bank Sta=5039.9,5043.9
Exp/Cntr=0.3,0.1

Type RM Length L Ch R = 1,2000,500,500,500
BEGIN DESCRIPTION:
SANFERNANDO056 4.0
END DESCRIPTION:
XS GIS Cut Line= 3
      2798255.68     10280653.11      2798304.15     10280420.10
      2797955.66     10279903.08
#Sta/Elev= 30
  4762.0 1228.75  4837.1 1224.27  4915.2 1215.38  4925.4 1212.70  4937.3 1212.38
  4956.1 1209.26  4976.5 1207.42  4982.3 1205.35  5002.3 1204.93  5002.6 1204.43
  5006.3 1204.93  5019.3 1207.28  5061.3 1210.58  5091.2 1217.63  5097.3 1217.37
  5112.2 1220.23  5118.3 1218.84  5148.2 1221.18  5154.3 1220.39  5169.2 1221.75
  5193.7 1226.53  5322.0 1238.82  5364.1 1245.59  5389.1 1247.94  5466.0 1258.39
  5487.0 1263.19  5514.9 1266.62  5544.0 1272.05  5574.0 1274.20  5623.5 1281.13
#Mann=5,-1,0
  4762.0    0.12       0  5002.3    0.07       0  5006.3    0.12       0
  5193.7    0.05       0  5389.1    0.12       0
Bank Sta=5002.3,5006.3
Exp/Cntr=0.3,0.1

Type RM Length L Ch R = 1,1500,252,252,252
BEGIN DESCRIPTION:
SANFERNANDO056 3.0
END DESCRIPTION:
XS GIS Cut Line= 3
      2798555.66     10280703.13      2798752.36     10280594.50
      2798855.69     10280403.11
#Sta/Elev= 30
  4775.3 1221.09  4802.2 1219.11  4810.8 1217.79  4842.9 1215.44  4848.7 1214.34
  4864.7 1213.74  4870.4 1212.40  4889.0 1210.71  4908.2 1209.13  4914.0 1207.66
  4927.0 1206.51  4935.7 1204.35  4946.1 1204.29  4951.8 1202.20  4967.8 1200.82
  4973.5 1197.61  4997.0 1197.03  4997.3 1196.53  5001.0 1197.03  5018.1 1197.58
  5024.3 1199.79  5040.0 1201.46  5047.0 1203.04  5083.7 1205.15  5121.8 1210.73
  5137.9 1212.07  5143.7 1213.45  5165.6 1215.61  5181.8 1218.18  5217.5 1221.47
#Mann=6,-1,0
  4775.3    0.05       0  4802.2    0.12       0  4889.0    0.05       0
  4927.0    0.12       0  4997.0    0.07       0  5001.0    0.12       0
Bank Sta=4997,5001
Exp/Cntr=0.3,0.1

Type RM Length L Ch R = 1,1248,438,438,438
BEGIN DESCRIPTION:
Mapping XS 3ae9fdcc
END DESCRIPTION:
XS GIS Cut Line= 3
      2798812.84     10280830.83      2798979.50     10280695.43
      2799083.67     10280419.35
#Sta/Elev= 30
  4733.8 1217.11  4817.3 1213.76  4848.0 1212.28  4912.0 1206.00  4918.4 1204.20
  4926.3 1203.55  4960.2 1197.88  4972.4 1196.82  4984.3 1194.22  5001.8 1193.16
  5002.1 1192.66  5005.8 1193.16  5009.2 1193.60  5015.1 1195.86  5057.9 1202.05
  5064.2 1204.70  5069.6 1204.25  5089.1 1207.42  5094.4 1207.17  5100.6 1208.44
  5111.3 1209.04  5119.3 1210.81  5124.6 1210.41  5149.4 1213.81  5154.8 1213.60
  5172.2 1215.67  5179.6 1215.47  5200.9 1218.14  5234.7 1220.64  5243.6 1220.14
#Mann=7,-1,0
  4733.8    0.12       0  4817.3    0.05       0  4960.2    0.12       0
  5001.8    0.07       0  5005.8    0.12       0  5172.2    0.05       0
  5200.9    0.12       0
Bank Sta=5001.8,5005.8
Exp/Cntr=0.3,0.1

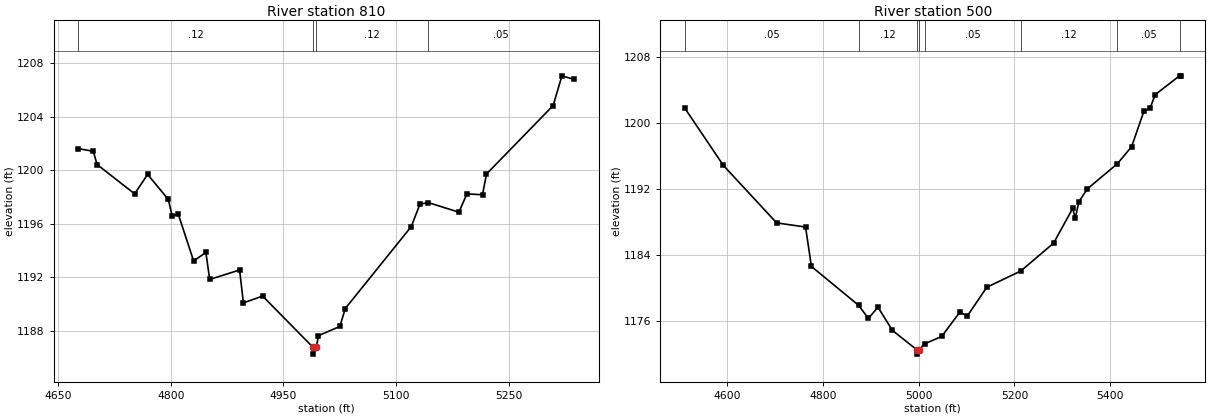
Type RM Length L Ch R = 1,810,310,310,310
BEGIN DESCRIPTION:
SANFERNANDO056 2.0
END DESCRIPTION:
XS GIS Cut Line= 3
      2799105.37     10280753.06      2799421.75     10280687.00
      2799312.97     10280367.72
#Sta/Elev= 30
  4676.8 1201.63  4696.7 1201.43  4701.8 1200.44  4751.8 1198.25  4769.1 1199.70
  4796.7 1197.83  4801.8 1196.59  4809.9 1196.74  4830.4 1193.23  4846.7 1193.87
  4851.8 1191.85  4891.6 1192.56  4896.7 1190.10  4922.3 1190.61  4989.6 1186.77
  4989.9 1186.27  4993.6 1186.77  4996.7 1187.65  5025.2 1188.34  5032.4 1189.68
  5120.3 1195.80  5131.8 1197.47  5142.7 1197.60  5183.7 1196.88  5194.5 1198.25
  5215.2 1198.18  5220.5 1199.73  5309.3 1204.85  5321.0 1207.07  5337.3 1206.80
#Mann=4,-1,0
  4676.8    0.12       0  4989.6    0.07       0  4993.6    0.12       0
  5142.7    0.05       0
Bank Sta=4989.6,4993.6
Exp/Cntr=0.3,0.1

Type RM Length L Ch R = 1,500,0,0,0
BEGIN DESCRIPTION:
SANFERNANDO056 1.0
END DESCRIPTION:
XS GIS Cut Line= 3
      2799105.67     10280853.11      2799589.98     10280918.45
      2799405.68     10280403.11
#Sta/Elev= 30
  4511.3 1201.85  4592.0 1194.90  4703.2 1187.94  4763.6 1187.44  4775.9 1182.66
  4874.8 1177.93  4894.8 1176.35  4914.9 1177.72  4945.2 1174.90  4996.7 1172.53
  4997.0 1172.03  5000.7 1172.53  5012.3 1173.27  5048.2 1174.18  5086.2 1177.14
  5101.3 1176.63  5142.4 1180.14  5213.1 1182.10  5281.8 1185.48  5321.8 1189.70
  5327.1 1188.51  5334.9 1190.52  5352.5 1192.07  5415.1 1195.11  5444.9 1197.18
  5470.4 1201.45  5483.6 1201.87  5494.2 1203.49  5545.1 1205.77  5547.3 1205.77
#Mann=8,-1,0
  4511.3    0.05       0  4874.8    0.12       0  4996.7    0.07       0
  5000.7    0.12       0  5012.3    0.05       0  5213.1    0.12       0
  5415.1    0.05       0  5545.1    0.12       0
Bank Sta=4996.7,5000.7
Exp/Cntr=0.3,0.1

Chan Stop Cuts=-1