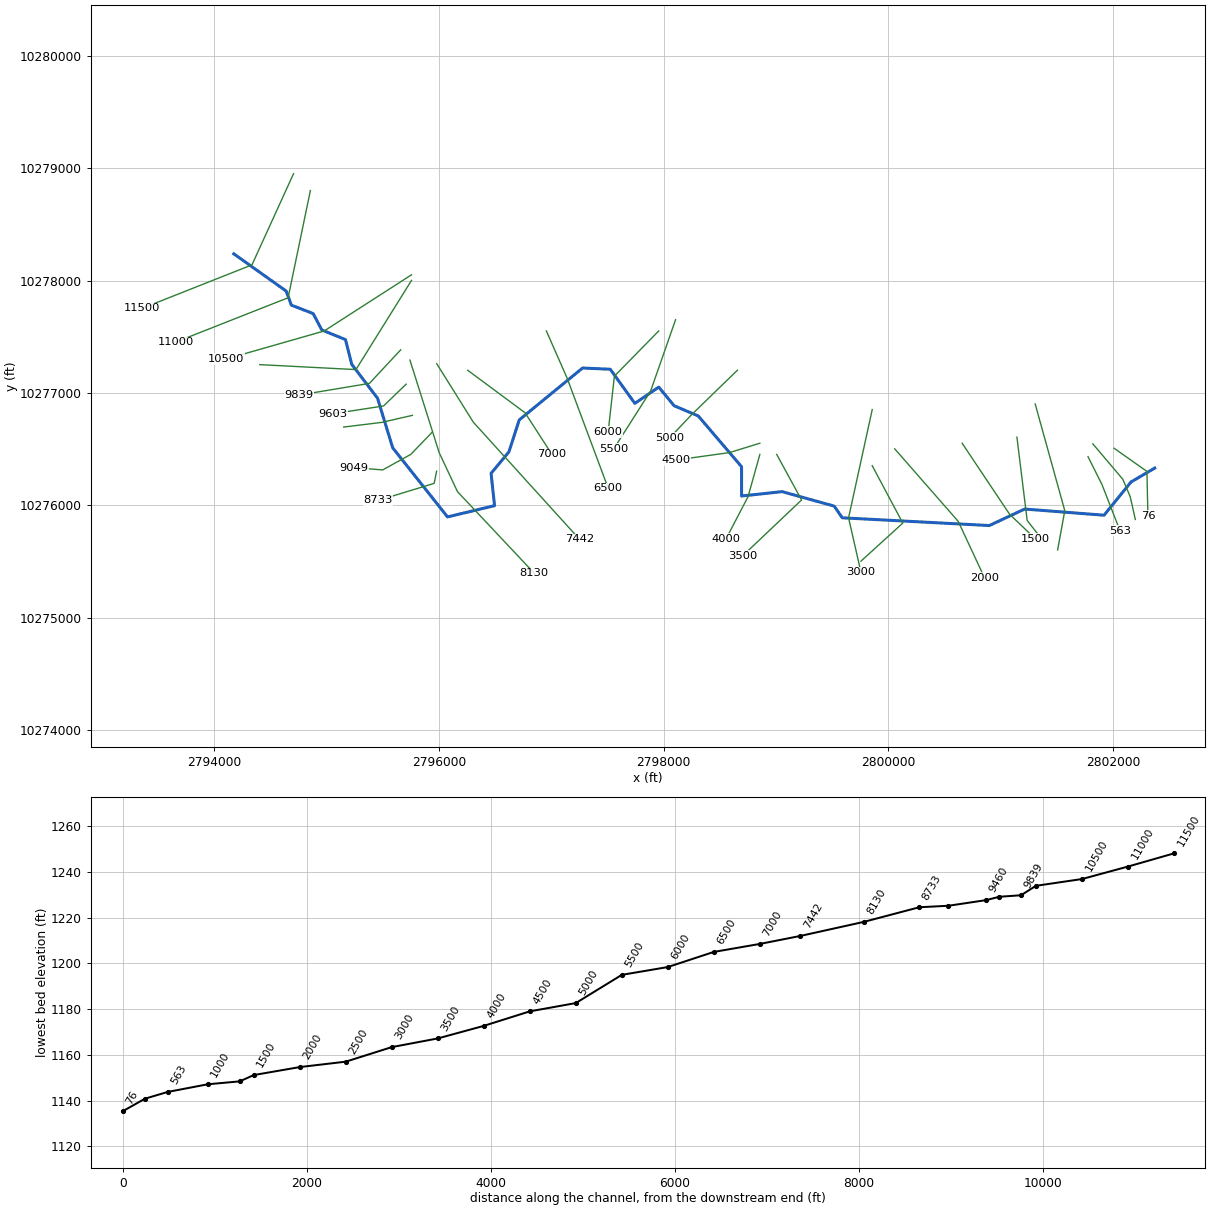
--- SANFERNANDO057.prj (project) ---

Proj Title=SANFERNANDO057 Base Level Engineering
Current Plan=p01
Default Exp/Contr=0.3,0.1
English Units
Geom File=g01
Flow File=f01
Plan File=p01
BEGIN DESCRIPTION:
SANFERNANDO057
END DESCRIPTION:

--- SANFERNANDO057.p01 (plan) ---

Plan Title=Multiple Run
Short Identifier=Multiple
Geom File=g01
Flow File=f01
Subcritical Flow
K Sum by GR= 0
Std Step Tol= 0.01
Critical Tol= 0.01
Num of Std Step Trials= 20
Max Error Tol= 0.3
Flow Tol Ratio= 0.001
Split Flow NTrial= 30
Split Flow Tol= 0.02
Split Flow Ratio= 0.02
Log Output Level= 0
Friction Slope Method= 1
Unsteady Friction Slope Method= 2
Unsteady Bridges Friction Slope Method= 1
Parabolic Critical Depth
Global Vel Dist=  1 , 1 , 1
Global Log Level= 0
CheckData=True
Encroach Param= -1, 0, 0, 0
BEGIN DESCRIPTION:
Multiple Run
END DESCRIPTION:

--- SANFERNANDO057.f01 (steady flow) ---

Flow Title=Multiple
Number of Profiles=7
Profile Names=10-year,25-year,50-year,1pct_min,100-year,1pct_plu,500-year
River Rch & RM= SANFERNANDO057,Reach-1,11500
     319     510     524     340     675    1336     912
River Rch & RM= SANFERNANDO057,Reach-1,5500
     498     819     985     581    1308    2944    1787
River Rch & RM= SANFERNANDO057,Reach-1,2000
     587     977    1214     828    1625    3192    2228
Boundary for River Rch & Prof#=SANFERNANDO057,Reach-1,1
Up Type=0
Dn Type=3
Dn Slope=0.005
Boundary for River Rch & Prof#=SANFERNANDO057,Reach-1,2
Up Type=0
Dn Type=3
Dn Slope=0.005
Boundary for River Rch & Prof#=SANFERNANDO057,Reach-1,3
Up Type=0
Dn Type=3
Dn Slope=0.005
Boundary for River Rch & Prof#=SANFERNANDO057,Reach-1,4
Up Type=0
Dn Type=3
Dn Slope=0.005
Boundary for River Rch & Prof#=SANFERNANDO057,Reach-1,5
Up Type=0
Dn Type=3
Dn Slope=0.005
Boundary for River Rch & Prof#=SANFERNANDO057,Reach-1,6
Up Type=0
Dn Type=3
Dn Slope=0.005
Boundary for River Rch & Prof#=SANFERNANDO057,Reach-1,7
Up Type=0
Dn Type=3
Dn Slope=0.005

--- SANFERNANDO057.g01 (geometry) ---

Geom Title=Existing Conditions

River Reach=SANFERNANDO057,Reach-1
Reach XY= 30
      2794174.25     10278240.00      2794640.50     10277908.00
      2794686.50     10277783.00      2794880.25     10277708.00
      2794957.25     10277562.00      2795167.75     10277476.00
      2795224.00     10277256.00      2795453.25     10276954.00
      2795588.50     10276512.00      2796076.00     10275897.00
      2796494.75     10275997.00      2796463.75     10276285.00
      2796622.50     10276476.00      2796714.50     10276761.00
      2797278.00     10277223.00      2797524.50     10277212.00
      2797743.25     10276908.00      2797956.00     10277053.00
      2798092.50     10276887.00      2798307.50     10276796.00
      2798692.75     10276344.00      2798693.00     10276083.00
      2799054.00     10276122.00      2799517.50     10275993.00
      2799588.75     10275889.00      2800897.75     10275820.00
      2801212.00     10275967.00      2801918.50     10275912.00
      2802158.75     10276208.00      2802370.00     10276332.00

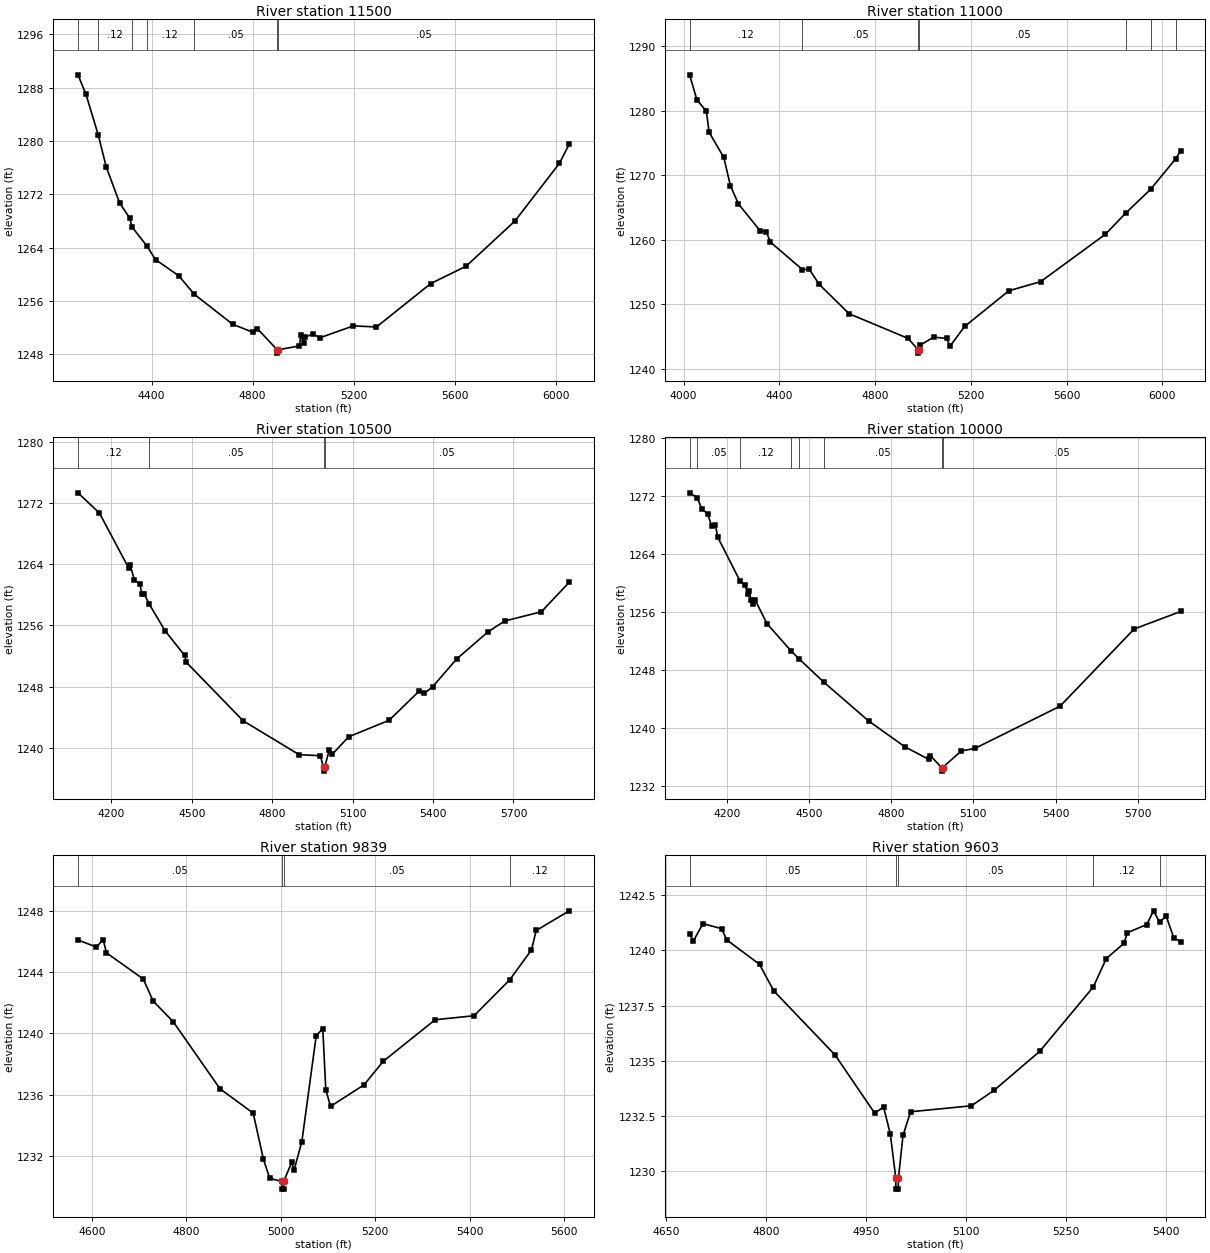
Type RM Length L Ch R = 1,11500,500,500,500
BEGIN DESCRIPTION:
SANFERNANDO057 23.0
END DESCRIPTION:
XS GIS Cut Line= 3
      2794705.68     10278953.11      2794335.99     10278141.66
      2793355.68     10277753.11
#Sta/Elev= 30
  4108.3 1289.92  4140.1 1286.98  4188.6 1280.90  4220.3 1276.10  4273.1 1270.72
  4312.5 1268.48  4322.8 1267.08  4379.8 1264.32  4416.0 1262.19  4507.8 1259.78
  4568.3 1257.03  4720.8 1252.52  4800.9 1251.31  4818.5 1251.86  4897.5 1248.68
  4897.8 1248.18  4901.5 1248.68  4985.3 1249.26  4990.8 1250.84  5002.9 1249.71
  5007.7 1250.55  5037.4 1251.05  5067.1 1250.49  5199.5 1252.27  5290.8 1252.10
  5505.9 1258.62  5645.7 1261.21  5839.4 1268.00  6015.3 1276.64  6054.5 1279.53
#Mann=7,-1,0
  4108.3    0.05       0  4188.6    0.12       0  4322.8    0.05       0
  4379.8    0.12       0  4568.3    0.05       0  4897.5    0.05       0
  4901.5    0.05       0
Bank Sta=4897.5,4901.5
Exp/Cntr=0.3,0.1

Type RM Length L Ch R = 1,11000,500,500,500
BEGIN DESCRIPTION:
SANFERNANDO057 22.0
END DESCRIPTION:
XS GIS Cut Line= 3
      2794855.68     10278803.10      2794657.66     10277848.72
      2793655.64     10277453.09
#Sta/Elev= 30
  4025.3 1285.56  4055.9 1281.68  4095.4 1279.93  4107.0 1276.65  4168.3 1272.75
  4195.7 1268.39  4229.5 1265.54  4321.5 1261.31  4346.1 1261.21  4362.3 1259.65
  4496.5 1255.37  4525.7 1255.39  4566.6 1253.08  4692.0 1248.51  4937.6 1244.70
  4980.7 1242.91  4980.9 1242.41  4984.7 1242.91  4987.8 1243.63  5045.1 1244.89
  5098.9 1244.69  5112.8 1243.47  5174.1 1246.54  5359.0 1252.08  5491.6 1253.49
  5762.1 1260.84  5846.6 1264.11  5951.0 1267.81  6055.4 1272.53  6077.3 1273.81
#Mann=7,-1,0
  4025.3    0.12       0  4496.5    0.05       0  4980.7    0.05       0
  4984.7    0.05       0  5846.6    0.12       0  5951.0    0.05       0
  6055.4    0.12       0
Bank Sta=4980.7,4984.7
Exp/Cntr=0.3,0.1

Type RM Length L Ch R = 1,10500,500,500,500
BEGIN DESCRIPTION:
SANFERNANDO057 21.0
END DESCRIPTION:
XS GIS Cut Line= 3
      2795755.65     10278053.09      2794978.64     10277552.87
      2794105.67     10277303.11
#Sta/Elev= 30
  4075.9 1273.33  4156.1 1270.68  4265.0 1263.49  4271.0 1263.85  4286.1 1261.94
  4307.3 1261.42  4313.7 1260.06  4322.5 1260.15  4340.3 1258.86  4401.0 1255.28
  4473.7 1252.07  4480.2 1251.17  4691.5 1243.54  4900.2 1239.11  4979.7 1238.96
  4991.9 1237.45  4992.2 1236.95  4995.9 1237.45  5012.8 1239.70  5023.9 1239.15
  5085.5 1241.44  5236.3 1243.60  5348.0 1247.40  5367.1 1247.10  5398.3 1247.97
  5488.3 1251.62  5606.3 1255.19  5667.6 1256.58  5804.0 1257.78  5908.0 1261.64
#Mann=4,-1,0
  4075.9    0.12       0  4340.3    0.05       0  4991.9    0.05       0
  4995.9    0.05       0
Bank Sta=4991.9,4995.9
Exp/Cntr=0.3,0.1

Type RM Length L Ch R = 1,10000,161,161,161
BEGIN DESCRIPTION:
SANFERNANDO057 20.0
END DESCRIPTION:
XS GIS Cut Line= 3
      2795755.70     10278003.14      2795261.26     10277208.87
      2794405.70     10277253.11
#Sta/Elev= 30
  4064.4 1272.38  4092.9 1271.69  4108.7 1270.17  4129.9 1269.51  4145.3 1267.80
  4158.7 1268.01  4166.5 1266.32  4249.1 1260.17  4266.8 1259.64  4276.3 1258.37
  4282.2 1258.80  4288.2 1257.62  4297.5 1257.07  4303.4 1257.61  4347.1 1254.31
  4435.0 1250.56  4464.9 1249.44  4553.9 1246.27  4717.7 1240.91  4848.7 1237.38
  4936.1 1235.62  4943.2 1236.11  4983.6 1234.49  4983.9 1233.99  4987.6 1234.49
  5055.6 1236.77  5105.7 1237.13  5416.1 1242.95  5686.5 1253.60  5856.7 1256.02
#Mann=8,-1,0
  4064.4    0.12       0  4092.9    0.05       0  4249.1    0.12       0
  4435.0    0.05       0  4464.9    0.12       0  4553.9    0.05       0
  4983.6    0.03       0  4987.6    0.05       0
Bank Sta=4983.6,4987.6
Exp/Cntr=0.3,0.1

Type RM Length L Ch R = 1,9839,236,236,236
BEGIN DESCRIPTION:
Mapping XS 324b807b
END DESCRIPTION:
XS GIS Cut Line= 3
      2795659.33     10277384.75      2795381.58     10277086.17
      2794756.60     10276982.00
#Sta/Elev= 30
  4570.0 1246.08  4609.2 1245.62  4623.4 1246.11  4630.2 1245.25  4708.4 1243.54
  4729.4 1242.10  4771.9 1240.76  4871.1 1236.39  4941.4 1234.81  4963.0 1231.82
  4976.5 1230.56  5002.1 1230.36  5002.3 1229.86  5005.8 1229.86  5006.1 1230.36
  5023.0 1231.61  5028.1 1231.10  5044.6 1232.96  5075.0 1239.85  5088.9 1240.31
  5095.3 1236.33  5105.4 1235.25  5176.4 1236.65  5217.0 1238.18  5327.2 1240.89
  5409.6 1241.15  5485.0 1243.48  5531.2 1245.43  5541.4 1246.70  5611.4 1247.98
#Mann=4,-1,0
  4570.0    0.05       0  5002.1    0.05       0  5006.1    0.05       0
  5485.0    0.12       0
Bank Sta=5002.1,5006.1
Exp/Cntr=0.3,0.1

Type RM Length L Ch R = 1,9603,143,143,143
BEGIN DESCRIPTION:
Mapping XS 2e8c9428
END DESCRIPTION:
XS GIS Cut Line= 3
      2795707.94     10277079.19      2795506.58     10276884.78
      2795055.19     10276815.33
#Sta/Elev= 30
  4685.2 1240.73  4691.0 1240.43  4705.2 1241.21  4733.5 1240.98  4740.7 1240.48
  4790.1 1239.37  4811.4 1238.17  4903.3 1235.27  4962.7 1232.64  4976.1 1232.91
  4986.2 1231.69  4994.4 1229.70  4994.6 1229.20  4998.1 1229.20  4998.4 1229.70
  5005.2 1231.63  5016.6 1232.70  5107.7 1232.97  5141.8 1233.67  5210.1 1235.43
  5290.6 1238.35  5310.0 1239.63  5336.5 1240.32  5341.6 1240.80  5370.7 1241.17
  5380.8 1241.79  5389.9 1241.28  5399.8 1241.55  5411.2 1240.57  5421.8 1240.39
#Mann=5,-1,0
  4685.2    0.05       0  4994.4    0.05       0  4998.4    0.05       0
  5290.6    0.12       0  5389.9    0.05       0
Bank Sta=4994.4,4998.4
Exp/Cntr=0.3,0.1

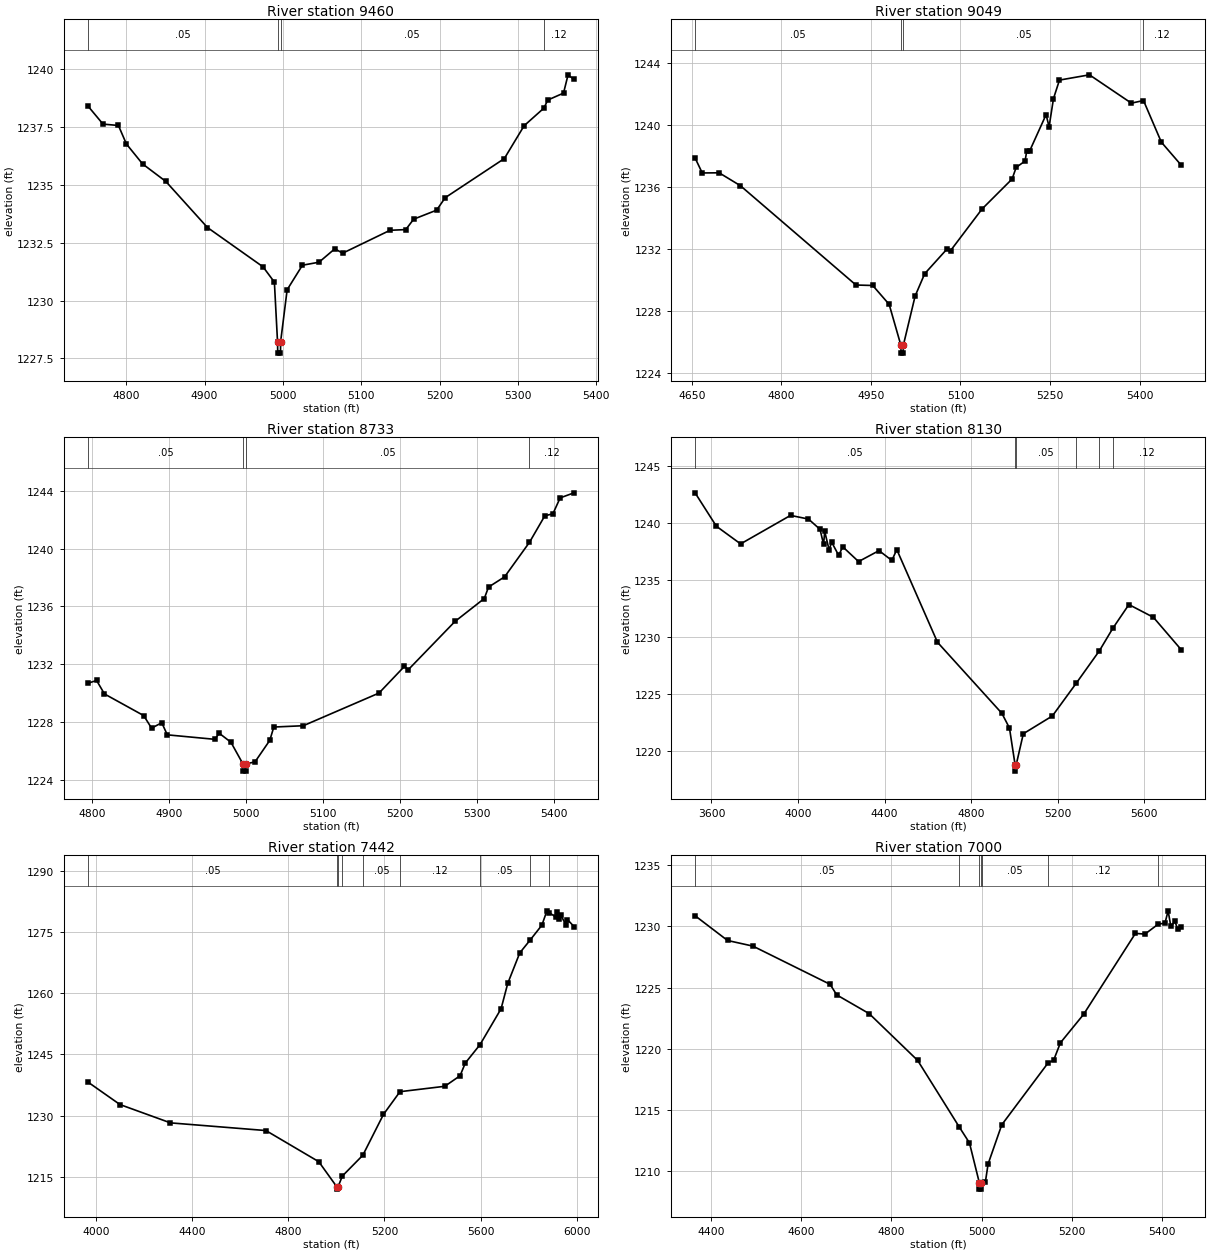
Type RM Length L Ch R = 1,9460,411,411,411
BEGIN DESCRIPTION:
Mapping XS 29320cda
END DESCRIPTION:
XS GIS Cut Line= 3
      2795763.55     10276801.45      2795492.69     10276738.94
      2795152.41     10276697.28
#Sta/Elev= 30
  4751.0 1238.41  4770.2 1237.63  4789.9 1237.57  4800.1 1236.77  4820.7 1235.91
  4850.5 1235.15  4903.6 1233.16  4974.6 1231.46  4989.1 1230.80  4993.1 1228.23
  4993.4 1227.73  4996.9 1227.73  4997.1 1228.23  5005.4 1230.47  5024.9 1231.53
  5046.1 1231.66  5066.3 1232.24  5076.3 1232.05  5136.8 1233.04  5156.9 1233.07
  5167.0 1233.52  5196.3 1233.91  5207.3 1234.45  5282.8 1236.14  5308.1 1237.56
  5333.3 1238.32  5338.3 1238.67  5358.4 1238.97  5364.2 1239.76  5371.8 1239.56
#Mann=4,-1,0
  4751.0    0.05       0  4993.1    0.03       0  4997.1    0.05       0
  5333.3    0.12       0
Bank Sta=4993.1,4997.1
Exp/Cntr=0.3,0.1

Type RM Length L Ch R = 1,9049,316,316,316
BEGIN DESCRIPTION:
Mapping XS 3db12d97
END DESCRIPTION:
XS GIS Cut Line= 4
      2795937.13     10276648.66      2795749.63     10276454.22
      2795499.63     10276315.33      2795242.68     10276336.17
#Sta/Elev= 30
  4655.6 1237.87  4667.6 1236.90  4695.9 1236.91  4731.4 1236.08  4925.0 1229.66
  4953.1 1229.63  4980.6 1228.41  5000.3 1225.76  5000.6 1225.26  5004.1 1225.26
  5004.3 1225.76  5024.1 1228.95  5040.1 1230.39  5077.8 1232.00  5083.6 1231.89
  5136.1 1234.57  5186.5 1236.51  5193.3 1237.26  5208.2 1237.67  5211.1 1238.35
  5216.2 1238.35  5243.4 1240.67  5248.4 1239.88  5255.8 1241.71  5265.8 1242.90
  5316.0 1243.24  5386.2 1241.41  5406.5 1241.58  5436.4 1238.89  5469.5 1237.41
#Mann=4,-1,0
  4655.6    0.05       0  5000.3    0.05       0  5004.3    0.05       0
  5406.5    0.12       0
Bank Sta=5000.3,5004.3
Exp/Cntr=0.3,0.1

Type RM Length L Ch R = 1,8733,603,603,603
BEGIN DESCRIPTION:
Mapping XS 60fee77a
END DESCRIPTION:
XS GIS Cut Line= 3
      2795979.06     10276304.14      2795957.36     10276195.64
      2795459.45     10276044.11
#Sta/Elev= 30
  4794.4 1230.69  4805.6 1230.88  4815.8 1229.95  4866.8 1228.45  4877.0 1227.58
  4890.2 1227.96  4897.4 1227.12  4959.1 1226.81  4964.8 1227.23  4980.0 1226.61
  4995.6 1225.11  4995.9 1224.61  4999.4 1224.61  4999.6 1225.11  5011.3 1225.25
  5030.5 1226.74  5035.7 1227.66  5074.0 1227.75  5172.3 1230.01  5205.2 1231.85
  5210.4 1231.63  5270.9 1234.96  5309.0 1236.55  5314.5 1237.34  5335.4 1238.05
  5367.7 1240.44  5387.6 1242.27  5398.1 1242.41  5407.5 1243.51  5425.5 1243.86
#Mann=4,-1,0
  4794.4    0.05       0  4995.6    0.05       0  4999.6    0.05       0
  5367.7    0.12       0
Bank Sta=4995.6,4999.6
Exp/Cntr=0.3,0.1

Type RM Length L Ch R = 1,8130,688,688,688
BEGIN DESCRIPTION:
Mapping XS 7ce2f35e
END DESCRIPTION:
XS GIS Cut Line= 4
      2795741.62     10277293.70      2796002.03     10276469.08
      2796164.79     10276121.86      2796848.35     10275394.89
#Sta/Elev= 30
  3524.1 1242.61  3622.5 1239.68  3734.5 1238.13  3965.2 1240.63  4048.1 1240.31
  4101.5 1239.41  4118.0 1238.09  4123.2 1239.22  4143.4 1237.62  4155.6 1238.27
  4187.9 1237.12  4206.4 1237.88  4279.6 1236.58  4374.1 1237.54  4433.5 1236.68
  4456.3 1237.63  4644.4 1229.50  4941.9 1223.27  4977.0 1221.98  5003.4 1218.70
  5003.6 1218.20  5007.4 1218.70  5041.0 1221.48  5175.3 1223.04  5285.2 1225.90
  5392.7 1228.76  5454.3 1230.72  5528.9 1232.81  5642.2 1231.69  5770.2 1228.86
#Mann=6,-1,0
  3524.1    0.05       0  5003.4    0.05       0  5007.4    0.05       0
  5285.2    0.12       0  5392.7    0.05       0  5454.3    0.12       0
Bank Sta=5003.4,5007.4
Exp/Cntr=0.3,0.1

Type RM Length L Ch R = 1,7442,442,442,442
BEGIN DESCRIPTION:
Mapping XS 42e88ecf
END DESCRIPTION:
XS GIS Cut Line= 3
      2795980.32     10277261.19      2796305.85     10276740.35
      2797249.87     10275698.67
#Sta/Elev= 30
  3967.9 1238.25  4101.0 1232.75  4310.9 1228.27  4707.5 1226.39  4927.2 1218.77
  5002.9 1212.56  5003.1 1212.06  5006.9 1212.56  5024.9 1215.25  5110.2 1220.35
  5196.1 1230.35  5264.6 1235.90  5450.9 1237.22  5514.4 1239.80  5536.1 1242.91
  5597.2 1247.40  5684.8 1256.19  5712.5 1262.39  5762.5 1269.86  5804.4 1272.91
  5854.4 1276.64  5875.3 1280.15  5884.2 1279.73  5911.2 1278.67  5917.9 1279.89
  5925.4 1278.04  5932.1 1279.22  5953.7 1276.75  5960.5 1278.02  5987.9 1276.30
#Mann=9,-1,0
  3967.9    0.05       0  5002.9    0.03       0  5006.9    0.05       0
  5024.9    0.12       0  5110.2    0.05       0  5264.6    0.12       0
  5597.2    0.05       0  5804.4    0.12       0  5884.2    0.05       0
Bank Sta=5002.9,5006.9
Exp/Cntr=0.3,0.1

Type RM Length L Ch R = 1,7000,500,500,500
BEGIN DESCRIPTION:
SANFERNANDO057 14.0
END DESCRIPTION:
XS GIS Cut Line= 3
      2796255.67     10277203.12      2796765.74     10276824.73
      2797005.71     10276453.07
#Sta/Elev= 30
  4364.9 1230.86  4436.9 1228.84  4493.2 1228.38  4664.3 1225.26  4678.9 1224.40
  4750.9 1222.87  4858.4 1219.05  4949.9 1213.66  4973.2 1212.32  4995.2 1209.05
  4995.4 1208.55  4998.9 1208.55  4999.2 1209.05  5000.0 1209.05  5008.5 1209.14
  5014.5 1210.60  5044.8 1213.80  5148.1 1218.88  5159.6 1219.05  5174.8 1220.49
  5226.2 1222.81  5341.1 1229.42  5362.2 1229.36  5391.9 1230.18  5406.6 1230.25
  5413.6 1231.26  5419.6 1230.00  5428.8 1230.40  5434.8 1229.74  5442.4 1229.98
#Mann=7,-1,0
  4364.9    0.05       0  4949.9    0.12       0  4995.2    0.07       0
  4999.2    0.12       0  5000.0    0.05       0  5148.1    0.12       0
  5391.9    0.05       0
Bank Sta=4995.2,4999.2
Exp/Cntr=0.3,0.1

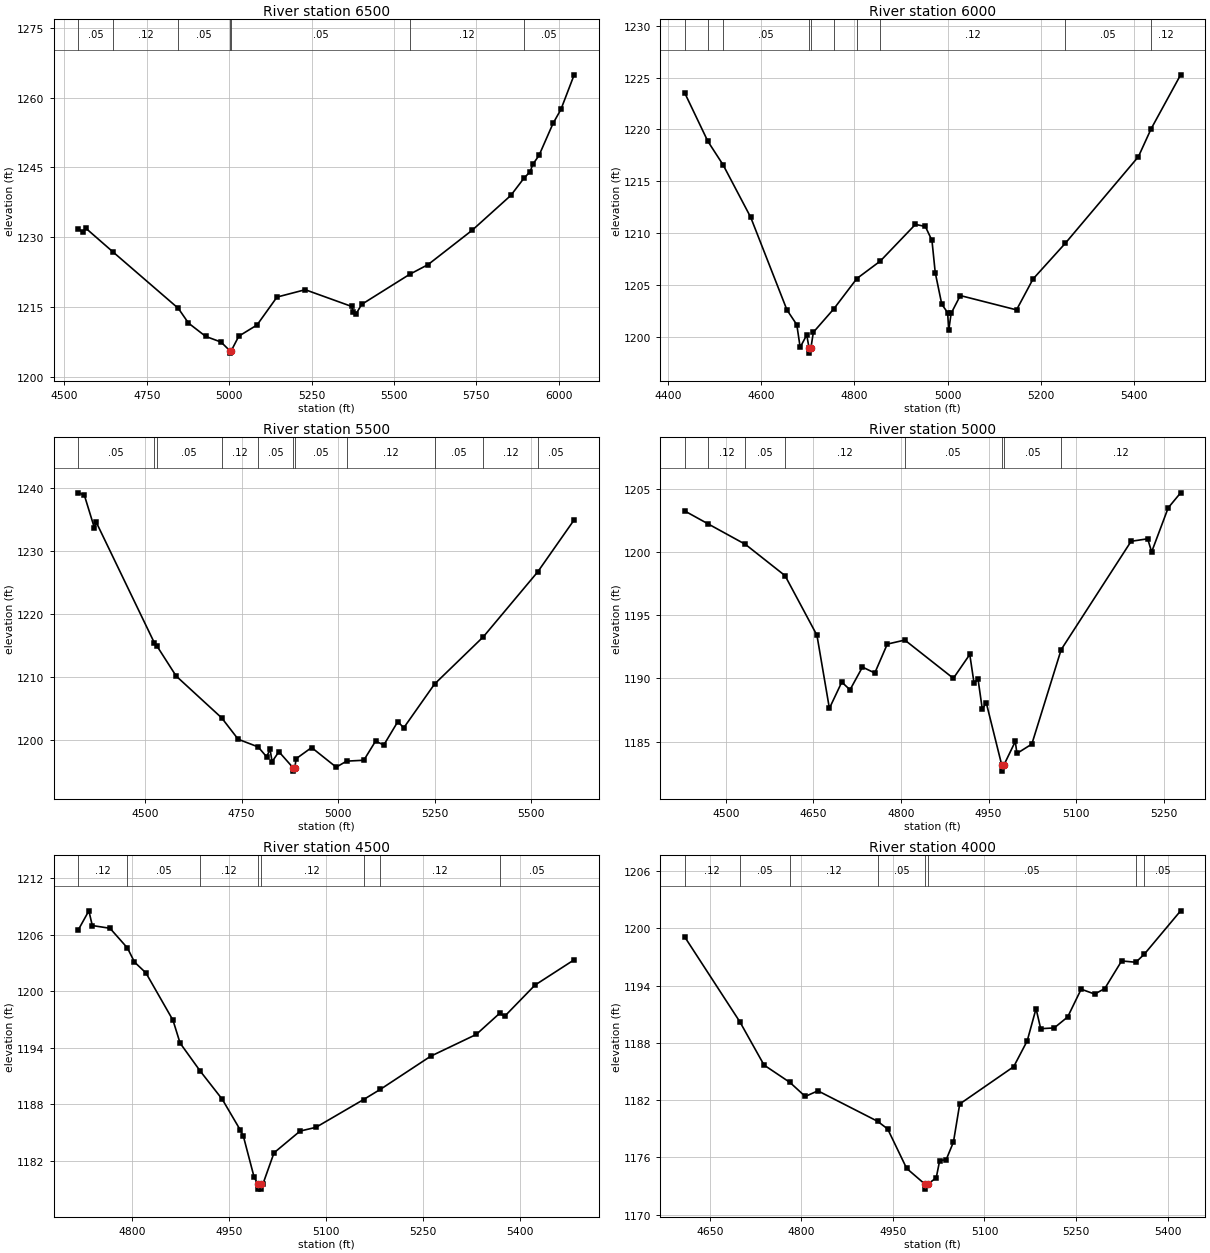
Type RM Length L Ch R = 1,6500,500,500,500
BEGIN DESCRIPTION:
SANFERNANDO057 13.0
END DESCRIPTION:
XS GIS Cut Line= 3
      2796955.69     10277553.11      2797140.03     10277133.84
      2797505.69     10276153.09
#Sta/Elev= 30
  4542.0 1231.72  4556.4 1231.09  4563.8 1231.97  4648.4 1226.74  4845.4 1214.68
  4876.3 1211.51  4928.4 1208.65  4975.1 1207.43  5002.0 1205.55  5002.2 1205.05
  5006.0 1205.55  5029.0 1208.70  5084.3 1211.10  5144.9 1217.11  5230.6 1218.69
  5371.5 1215.09  5376.8 1213.87  5385.0 1213.51  5401.8 1215.53  5547.9 1222.02
  5603.4 1224.09  5737.2 1231.48  5854.6 1238.98  5893.7 1242.62  5913.3 1244.10
  5920.9 1245.63  5940.0 1247.56  5982.6 1254.46  6006.5 1257.46  6046.7 1264.91
#Mann=7,-1,0
  4542.0    0.05       0  4648.4    0.12       0  4845.4    0.05       0
  5002.0    0.05       0  5006.0    0.05       0  5547.9    0.12       0
  5893.7    0.05       0
Bank Sta=5002,5006
Exp/Cntr=0.3,0.1

Type RM Length L Ch R = 1,6000,500,500,500
BEGIN DESCRIPTION:
SANFERNANDO057 12.0
END DESCRIPTION:
XS GIS Cut Line= 3
      2797955.71     10277553.14      2797561.00     10277150.14
      2797505.68     10276653.10
#Sta/Elev= 30
  4435.9 1223.50  4485.4 1218.85  4518.1 1216.58  4577.3 1211.53  4655.2 1202.59
  4676.3 1201.17  4683.5 1198.99  4697.6 1200.18  4702.6 1198.93  4702.9 1198.43
  4706.6 1198.93  4711.8 1200.44  4755.8 1202.70  4805.2 1205.62  4855.4 1207.30
  4930.9 1210.84  4952.2 1210.64  4966.4 1209.29  4973.4 1206.20  4987.5 1203.13
  5000.0 1202.34  5002.4 1200.63  5007.5 1202.26  5027.2 1203.98  5147.9 1202.60
  5183.4 1205.58  5252.6 1209.02  5409.5 1217.37  5436.6 1220.04  5500.1 1225.26
#Mann=10,-1,0
  4435.9    0.05       0  4485.4    0.12       0  4518.1    0.05       0
  4702.6    0.07       0  4706.6    0.05       0  4755.8    0.12       0
  4805.2    0.05       0  4855.4    0.12       0  5252.6    0.05       0
  5436.6    0.12       0
Bank Sta=4702.6,4706.6
Exp/Cntr=0.3,0.1

Type RM Length L Ch R = 1,5500,500,500,500
BEGIN DESCRIPTION:
SANFERNANDO057 11.0
END DESCRIPTION:
XS GIS Cut Line= 3
      2798105.68     10277653.11      2797883.66     10277018.21
      2797555.66     10276503.07
#Sta/Elev= 30
  4327.4 1239.27  4342.9 1238.91  4368.7 1233.75  4374.0 1234.56  4523.8 1215.46
  4530.2 1214.97  4580.6 1210.13  4698.4 1203.48  4741.1 1200.08  4792.8 1198.86
  4814.7 1197.29  4823.6 1198.48  4828.9 1196.51  4846.5 1198.10  4883.7 1195.51
  4884.0 1195.01  4887.7 1195.51  4891.0 1196.98  4931.2 1198.76  4994.8 1195.64
  5021.8 1196.60  5066.3 1196.74  5096.8 1199.79  5118.0 1199.16  5154.4 1202.89
  5169.6 1201.89  5249.4 1208.86  5375.9 1216.39  5516.3 1226.69  5610.7 1234.97
#Mann=11,-1,0
  4327.4    0.05       0  4523.8    0.12       0  4530.2    0.05       0
  4698.4    0.12       0  4792.8    0.05       0  4883.7    0.05       0
  4887.7    0.05       0  5021.8    0.12       0  5249.4    0.05       0
  5375.9    0.12       0  5516.3    0.05       0
Bank Sta=4883.7,4887.7
Exp/Cntr=0.3,0.1

Type RM Length L Ch R = 1,5000,500,500,500
BEGIN DESCRIPTION:
SANFERNANDO057 10.0
END DESCRIPTION:
XS GIS Cut Line= 3
      2798655.67     10277203.09      2798246.74     10276806.00
      2798055.68     10276603.10
#Sta/Elev= 30
  4430.0 1203.26  4469.5 1202.25  4533.7 1200.62  4601.6 1198.14  4656.2 1193.42
  4677.5 1187.63  4698.7 1189.71  4712.8 1189.10  4734.1 1190.90  4755.2 1190.43
  4776.6 1192.72  4806.6 1193.04  4889.7 1190.01  4917.8 1191.90  4925.0 1189.66
  4932.0 1189.92  4939.2 1187.58  4946.1 1188.06  4972.4 1183.16  4972.7 1182.66
  4976.4 1183.16  4995.7 1185.01  4998.5 1184.06  5024.0 1184.80  5074.2 1192.28
  5193.9 1200.86  5222.3 1201.06  5229.1 1200.02  5257.4 1203.51  5278.7 1204.70
#Mann=8,-1,0
  4430.0    0.05       0  4469.5    0.12       0  4533.7    0.05       0
  4601.6    0.12       0  4806.6    0.05       0  4972.4    0.05       0
  4976.4    0.05       0  5074.2    0.12       0
Bank Sta=4972.4,4976.4
Exp/Cntr=0.3,0.1

Type RM Length L Ch R = 1,4500,500,500,500
BEGIN DESCRIPTION:
SANFERNANDO057 9.0
END DESCRIPTION:
XS GIS Cut Line= 3
      2798855.68     10276553.11      2798585.06     10276469.62
      2798105.65     10276403.11
#Sta/Elev= 30
  4716.8 1206.51  4733.1 1208.52  4738.4 1206.96  4765.8 1206.67  4792.7 1204.59
  4803.7 1203.09  4821.4 1201.94  4863.3 1196.92  4874.2 1194.51  4905.6 1191.52
  4939.5 1188.55  4967.0 1185.34  4972.2 1184.63  4988.9 1180.27  4995.1 1179.53
  4995.3 1179.03  4998.8 1179.03  4999.1 1179.53  5002.2 1179.53  5019.6 1182.88
  5059.9 1185.18  5084.5 1185.58  5158.1 1188.52  5184.3 1189.61  5261.9 1193.11
  5332.5 1195.42  5368.7 1197.66  5376.4 1197.34  5423.4 1200.65  5484.0 1203.33
#Mann=8,-1,0
  4716.8    0.12       0  4792.7    0.05       0  4905.6    0.12       0
  4995.1    0.07       0  4999.1    0.12       0  5158.1    0.05       0
  5184.3    0.12       0  5368.7    0.05       0
Bank Sta=4995.1,4999.1
Exp/Cntr=0.3,0.1

Type RM Length L Ch R = 1,4000,500,500,500
BEGIN DESCRIPTION:
SANFERNANDO057 8.0
END DESCRIPTION:
XS GIS Cut Line= 3
      2798855.67     10276453.08      2798750.37     10276076.73
      2798555.68     10275703.11
#Sta/Elev= 30
  4609.2 1199.09  4699.4 1190.21  4739.0 1185.68  4781.4 1183.86  4806.5 1182.39
  4827.2 1182.98  4924.9 1179.79  4941.5 1178.98  4972.6 1174.85  5002.9 1173.18
  5003.1 1172.68  5006.9 1173.18  5021.0 1173.87  5026.6 1175.65  5037.4 1175.78
  5049.2 1177.61  5059.5 1181.60  5147.9 1185.51  5170.0 1188.21  5184.5 1191.59
  5192.1 1189.49  5214.2 1189.57  5236.3 1190.72  5258.4 1193.63  5280.5 1193.12
  5297.0 1193.69  5324.7 1196.59  5348.0 1196.45  5362.0 1197.31  5421.3 1201.84
#Mann=8,-1,0
  4609.2    0.12       0  4699.4    0.05       0  4781.4    0.12       0
  4924.9    0.05       0  5002.9    0.05       0  5006.9    0.05       0
  5348.0    0.12       0  5362.0    0.05       0
Bank Sta=5002.9,5006.9
Exp/Cntr=0.3,0.1

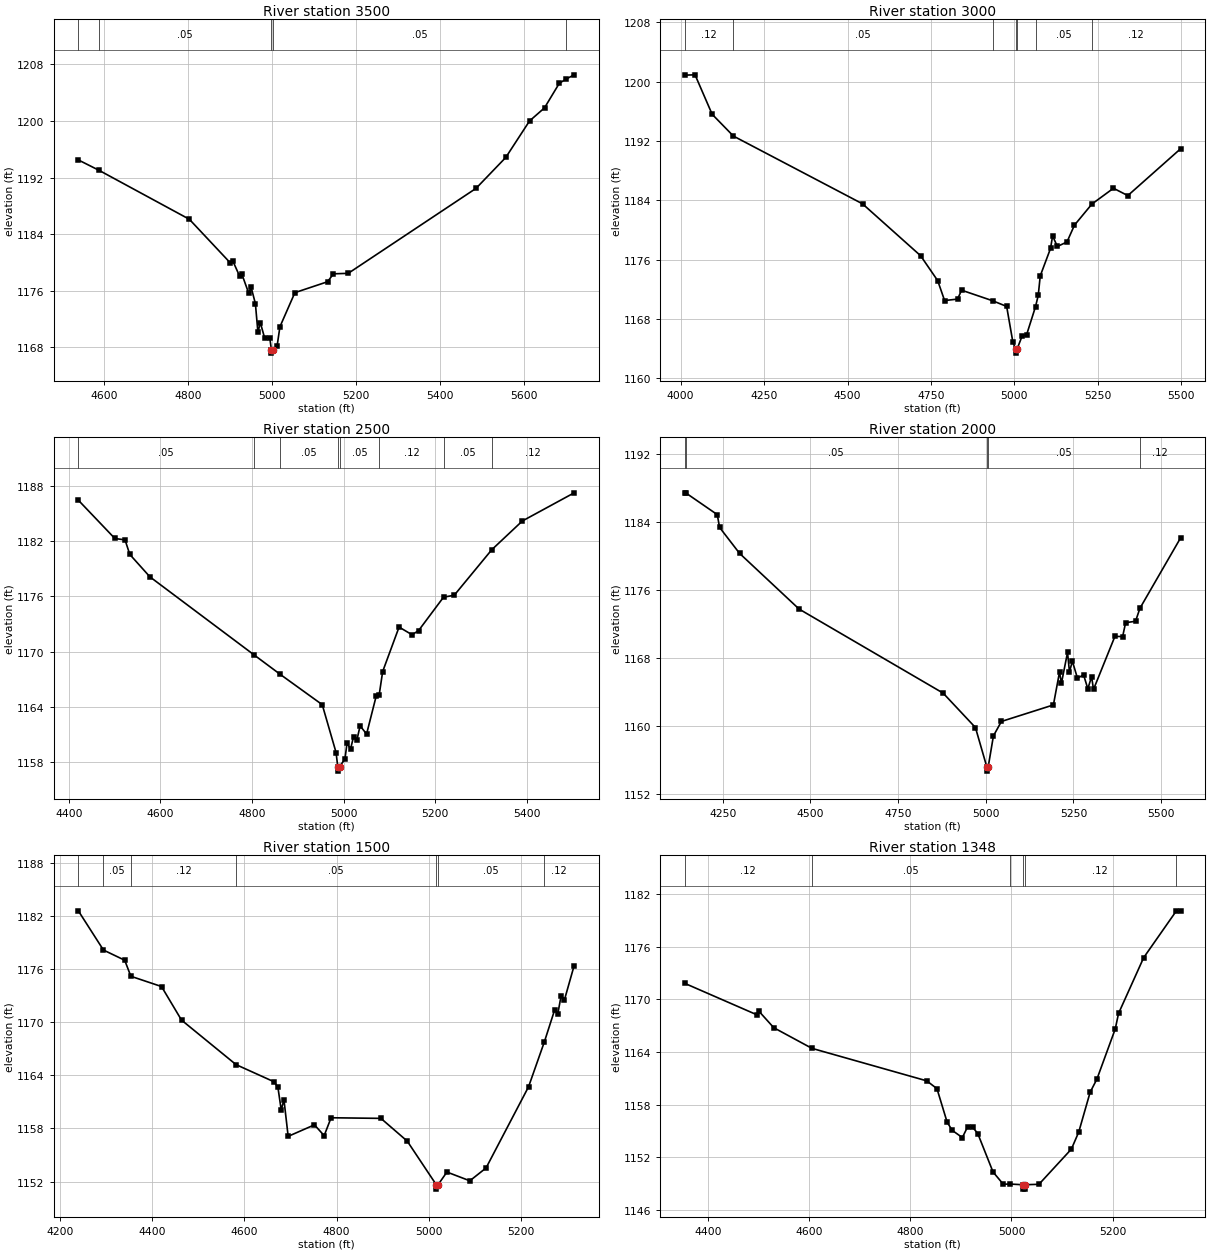
Type RM Length L Ch R = 1,3500,500,500,500
BEGIN DESCRIPTION:
SANFERNANDO057 7.0
END DESCRIPTION:
XS GIS Cut Line= 3
      2799005.70     10276453.08      2799226.89     10276047.93
      2798705.67     10275553.10
#Sta/Elev= 30
  4538.4 1194.49  4587.7 1193.02  4802.7 1186.10  4900.4 1179.92  4906.1 1180.21
  4922.2 1178.08  4927.9 1178.31  4944.1 1175.63  4949.8 1176.47  4959.9 1174.18
  4965.9 1170.12  4971.6 1171.49  4982.0 1169.30  4994.1 1169.36  4997.9 1167.68
  4998.1 1167.18  5001.9 1167.68  5011.4 1168.12  5018.3 1170.91  5053.9 1175.73
  5131.6 1177.27  5145.7 1178.39  5180.9 1178.46  5485.1 1190.47  5555.9 1194.84
  5612.5 1200.00  5648.1 1201.85  5683.3 1205.32  5698.6 1205.89  5718.7 1206.52
#Mann=5,-1,0
  4538.4    0.12       0  4587.7    0.05       0  4997.9    0.05       0
  5001.9    0.05       0  5698.6    0.12       0
Bank Sta=4997.9,5001.9
Exp/Cntr=0.3,0.1

Type RM Length L Ch R = 1,3000,500,500,500
BEGIN DESCRIPTION:
SANFERNANDO057 6.0
END DESCRIPTION:
XS GIS Cut Line= 3
      2799855.69     10276853.14      2799645.03     10275888.48
      2799755.68     10275403.13
#Sta/Elev= 30
  4012.6 1200.88  4043.3 1200.92  4094.5 1195.60  4158.2 1192.66  4544.9 1183.52
  4718.9 1176.52  4770.1 1173.16  4790.8 1170.47  4829.6 1170.67  4841.7 1171.87
  4934.3 1170.45  4976.7 1169.68  4995.1 1164.92  5003.5 1163.88  5003.8 1163.38
  5007.5 1163.88  5023.2 1165.71  5036.3 1165.84  5063.1 1169.64  5071.3 1171.17
  5077.3 1173.80  5108.1 1177.50  5114.3 1179.19  5128.6 1177.77  5157.3 1178.37
  5179.9 1180.65  5232.1 1183.49  5296.6 1185.62  5339.6 1184.63  5497.8 1190.95
#Mann=7,-1,0
  4012.6    0.12       0  4158.2    0.05       0  4934.3    0.12       0
  5003.5    0.07       0  5007.5    0.12       0  5063.1    0.05       0
  5232.1    0.12       0
Bank Sta=5003.5,5007.5
Exp/Cntr=0.3,0.1

Type RM Length L Ch R = 1,2500,500,500,500
BEGIN DESCRIPTION:
SANFERNANDO057 5.0
END DESCRIPTION:
XS GIS Cut Line= 3
      2799855.70     10276353.09      2800127.62     10275841.80
      2799755.72     10275503.14
#Sta/Elev= 30
  4420.9 1186.44  4500.6 1182.28  4522.8 1182.13  4533.2 1180.55  4577.2 1178.11
  4804.3 1169.64  4861.8 1167.51  4953.2 1164.23  4983.4 1159.03  4987.0 1157.51
  4987.3 1157.01  4991.0 1157.51  5002.7 1158.31  5007.4 1160.07  5014.9 1159.40
  5021.6 1160.75  5029.1 1160.44  5035.8 1161.93  5050.0 1161.04  5071.0 1165.17
  5077.5 1165.30  5085.1 1167.83  5120.9 1172.66  5149.3 1171.82  5163.5 1172.28
  5218.0 1175.91  5241.2 1176.11  5323.2 1181.06  5389.9 1184.18  5503.0 1187.24
#Mann=8,-1,0
  4420.9    0.05       0  4804.3    0.12       0  4861.8    0.05       0
  4987.0    0.03       0  4991.0    0.05       0  5077.5    0.12       0
  5218.0    0.05       0  5323.2    0.12       0
Bank Sta=4987,4991
Exp/Cntr=0.3,0.1

Type RM Length L Ch R = 1,2000,500,500,500
BEGIN DESCRIPTION:
SANFERNANDO057 4.0
END DESCRIPTION:
XS GIS Cut Line= 3
      2800055.67     10276503.13      2800621.10     10275857.14
      2800855.67     10275353.15
#Sta/Elev= 30
  4141.5 1187.47  4144.0 1187.47  4234.1 1184.90  4240.7 1183.39  4297.7 1180.33
  4467.5 1173.76  4878.5 1163.84  4970.6 1159.78  5003.0 1155.14  5003.2 1154.64
  5007.0 1155.14  5021.9 1158.80  5044.7 1160.50  5193.0 1162.45  5210.4 1166.32
  5215.9 1165.01  5233.3 1168.64  5238.8 1166.34  5247.1 1167.61  5261.7 1165.59
  5279.0 1166.01  5291.2 1164.35  5301.9 1165.79  5307.4 1164.28  5368.4 1170.53
  5390.5 1170.52  5399.0 1172.15  5427.3 1172.32  5439.8 1173.85  5555.9 1182.16
#Mann=5,-1,0
  4141.5    0.12       0  4144.0    0.05       0  5003.0    0.05       0
  5007.0    0.05       0  5439.8    0.12       0
Bank Sta=5003,5007
Exp/Cntr=0.3,0.1

Type RM Length L Ch R = 1,1500,152,152,152
BEGIN DESCRIPTION:
SANFERNANDO057 3.0
END DESCRIPTION:
XS GIS Cut Line= 3
      2800655.69     10276553.11      2801077.73     10275921.06
      2801305.70     10275703.10
#Sta/Elev= 30
  4240.0 1182.57  4294.5 1178.14  4340.6 1176.99  4353.9 1175.18  4420.4 1174.02
  4463.8 1170.23  4582.1 1165.20  4665.0 1163.25  4672.9 1162.63  4680.0 1160.10
  4686.0 1161.22  4695.1 1157.10  4752.1 1158.40  4773.2 1157.18  4788.2 1159.20
  4896.3 1159.13  4953.4 1156.56  5016.3 1151.64  5016.6 1151.14  5020.3 1151.64
  5039.4 1153.07  5089.1 1152.08  5124.3 1153.53  5216.5 1162.70  5250.9 1167.79
  5273.1 1171.38  5280.0 1170.96  5287.2 1173.00  5294.2 1172.49  5315.4 1176.39
#Mann=7,-1,0
  4240.0    0.12       0  4294.5    0.05       0  4353.9    0.12       0
  4582.1    0.05       0  5016.3    0.05       0  5020.3    0.05       0
  5250.9    0.12       0
Bank Sta=5016.3,5020.3
Exp/Cntr=0.3,0.1

Type RM Length L Ch R = 1,1348,348,348,348
BEGIN DESCRIPTION:
Mapping XS 1c9e9dfb
END DESCRIPTION:
XS GIS Cut Line= 3
      2801143.28     10276607.59      2801234.42     10275865.42
      2801377.67     10275683.11
#Sta/Elev= 30
  4354.6 1171.82  4496.3 1168.26  4501.3 1168.63  4530.4 1166.77  4605.8 1164.42
  4832.6 1160.72  4852.8 1159.83  4872.9 1156.01  4883.0 1155.08  4902.9 1154.26
  4913.2 1155.46  4923.3 1155.44  4933.4 1154.72  4963.6 1150.34  4983.8 1148.95
  4997.2 1148.97  5021.9 1148.89  5022.2 1148.39  5025.9 1148.39  5026.2 1148.89
  5054.3 1148.94  5118.4 1152.95  5132.9 1154.89  5155.4 1159.42  5168.9 1160.93
  5205.1 1166.64  5211.5 1168.39  5261.2 1174.75  5325.0 1180.01  5334.2 1180.08
#Mann=6,-1,0
  4354.6    0.12       0  4605.8    0.05       0  4997.2    0.12       0
  5021.9    0.07       0  5026.2    0.12       0  5325.0    0.05       0
Bank Sta=5021.9,5026.2
Exp/Cntr=0.3,0.1

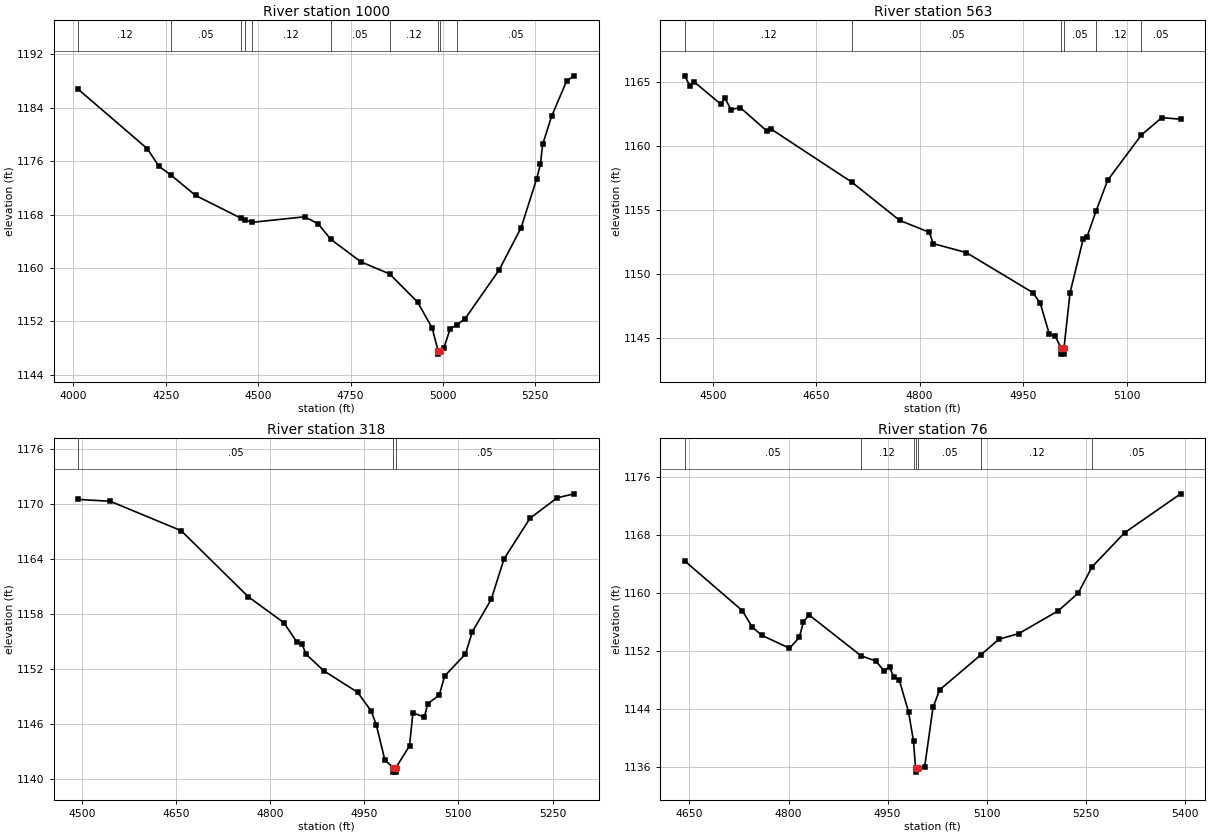
Type RM Length L Ch R = 1,1000,437,437,437
BEGIN DESCRIPTION:
SANFERNANDO057 2.0
END DESCRIPTION:
XS GIS Cut Line= 3
      2801305.70     10276903.07      2801569.20     10275952.42
      2801505.69     10275603.14
#Sta/Elev= 30
  4013.5 1186.74  4200.2 1177.86  4231.4 1175.23  4264.2 1173.91  4330.8 1170.86
  4453.9 1167.45  4465.6 1167.23  4482.4 1166.83  4625.7 1167.67  4662.0 1166.63
  4696.5 1164.30  4778.5 1160.91  4855.9 1159.11  4931.2 1154.91  4970.7 1151.04
  4986.8 1147.61  4987.0 1147.11  4991.1 1147.61  5002.2 1148.00  5019.6 1150.90
  5037.9 1151.49  5060.3 1152.44  5151.8 1159.69  5211.5 1166.04  5253.4 1173.32
  5263.6 1175.51  5269.9 1178.54  5294.0 1182.71  5334.7 1188.01  5355.0 1188.77
#Mann=10,-1,0
  4013.5    0.12       0  4264.2    0.05       0  4453.9    0.12       0
  4465.6    0.05       0  4482.4    0.12       0  4696.5    0.05       0
  4855.9    0.12       0  4986.8    0.07       0  4991.1    0.12       0
  5037.9    0.05       0
Bank Sta=4986.8,4991.1
Exp/Cntr=0.3,0.1

Type RM Length L Ch R = 1,563,245,245,245
BEGIN DESCRIPTION:
Mapping XS 48c917b8
END DESCRIPTION:
XS GIS Cut Line= 3
      2801776.19     10276432.94      2801901.20     10276182.93
      2802060.82     10275773.47
#Sta/Elev= 30
  4459.4 1165.50  4467.1 1164.67  4472.7 1165.04  4511.9 1163.27  4517.4 1163.79
  4526.3 1162.86  4539.8 1163.02  4578.9 1161.16  4584.5 1161.34  4702.0 1157.17
  4770.9 1154.20  4813.9 1153.27  4819.7 1152.38  4867.5 1151.68  4964.1 1148.55
  4974.9 1147.72  4988.1 1145.28  4996.3 1145.16  5004.9 1144.24  5005.2 1143.74
  5009.0 1143.74  5009.3 1144.24  5018.0 1148.52  5037.1 1152.74  5042.5 1152.89
  5055.9 1154.94  5072.4 1157.32  5121.6 1160.88  5151.2 1162.23  5178.4 1162.11
#Mann=6,-1,0
  4459.4    0.12       0  4702.0    0.05       0  5004.9    0.05       0
  5009.3    0.05       0  5055.9    0.12       0  5121.6    0.05       0
Bank Sta=5004.9,5009.3
Exp/Cntr=0.3,0.1

Type RM Length L Ch R = 1,318,242,242,242
BEGIN DESCRIPTION:
Mapping XS ef397770
END DESCRIPTION:
XS GIS Cut Line= 4
      2801818.62     10276547.71      2802085.98     10276231.74
      2802151.96     10276075.49      2802197.09     10275874.10
#Sta/Elev= 30
  4494.5 1170.51  4545.3 1170.31  4658.4 1167.10  4765.0 1159.92  4822.1 1157.07
  4843.0 1154.93  4850.7 1154.79  4857.3 1153.64  4885.8 1151.83  4939.5 1149.49
  4961.2 1147.45  4969.3 1145.91  4982.9 1142.10  4996.2 1141.30  4996.5 1140.80
  5000.3 1140.80  5000.6 1141.30  5022.1 1143.66  5027.5 1147.25  5045.8 1146.80
  5051.2 1148.26  5069.5 1149.19  5078.0 1151.26  5111.2 1153.67  5122.2 1156.09
  5152.2 1159.61  5172.7 1164.03  5214.1 1168.46  5257.4 1170.69  5284.4 1171.12
#Mann=3,-1,0
  4494.5    0.05       0  4996.2    0.05       0  5000.6    0.05       0
Bank Sta=4996.2,5000.6
Exp/Cntr=0.3,0.1

Type RM Length L Ch R = 1,76,0,0,0
BEGIN DESCRIPTION:
SANFERNANDO057 1.0
END DESCRIPTION:
XS GIS Cut Line= 3
      2802008.79     10276507.97      2802300.50     10276302.00
      2802308.75     10275908.09
#Sta/Elev= 30
  4642.9 1164.38  4730.1 1157.54  4744.9 1155.30  4759.7 1154.14  4801.5 1152.37
  4816.3 1153.85  4822.7 1155.99  4831.1 1156.96  4910.0 1151.32  4932.1 1150.62
  4945.1 1149.22  4953.0 1149.80  4959.1 1148.47  4967.8 1147.98  4981.9 1143.58
  4989.4 1139.55  4992.5 1135.81  4992.8 1135.31  4996.9 1135.81  5006.3 1136.06
  5018.9 1144.21  5028.9 1146.64  5091.7 1151.48  5118.9 1153.61  5148.9 1154.39
  5208.9 1157.54  5238.9 1159.97  5259.9 1163.58  5309.0 1168.26  5394.0 1173.63
#Mann=7,-1,0
  4642.9    0.05       0  4910.0    0.12       0  4989.4    0.05       0
  4992.5    0.05       0  4996.9    0.05       0  5091.7    0.12       0
  5259.9    0.05       0
Bank Sta=4992.5,4996.9
Exp/Cntr=0.3,0.1

Chan Stop Cuts=-1