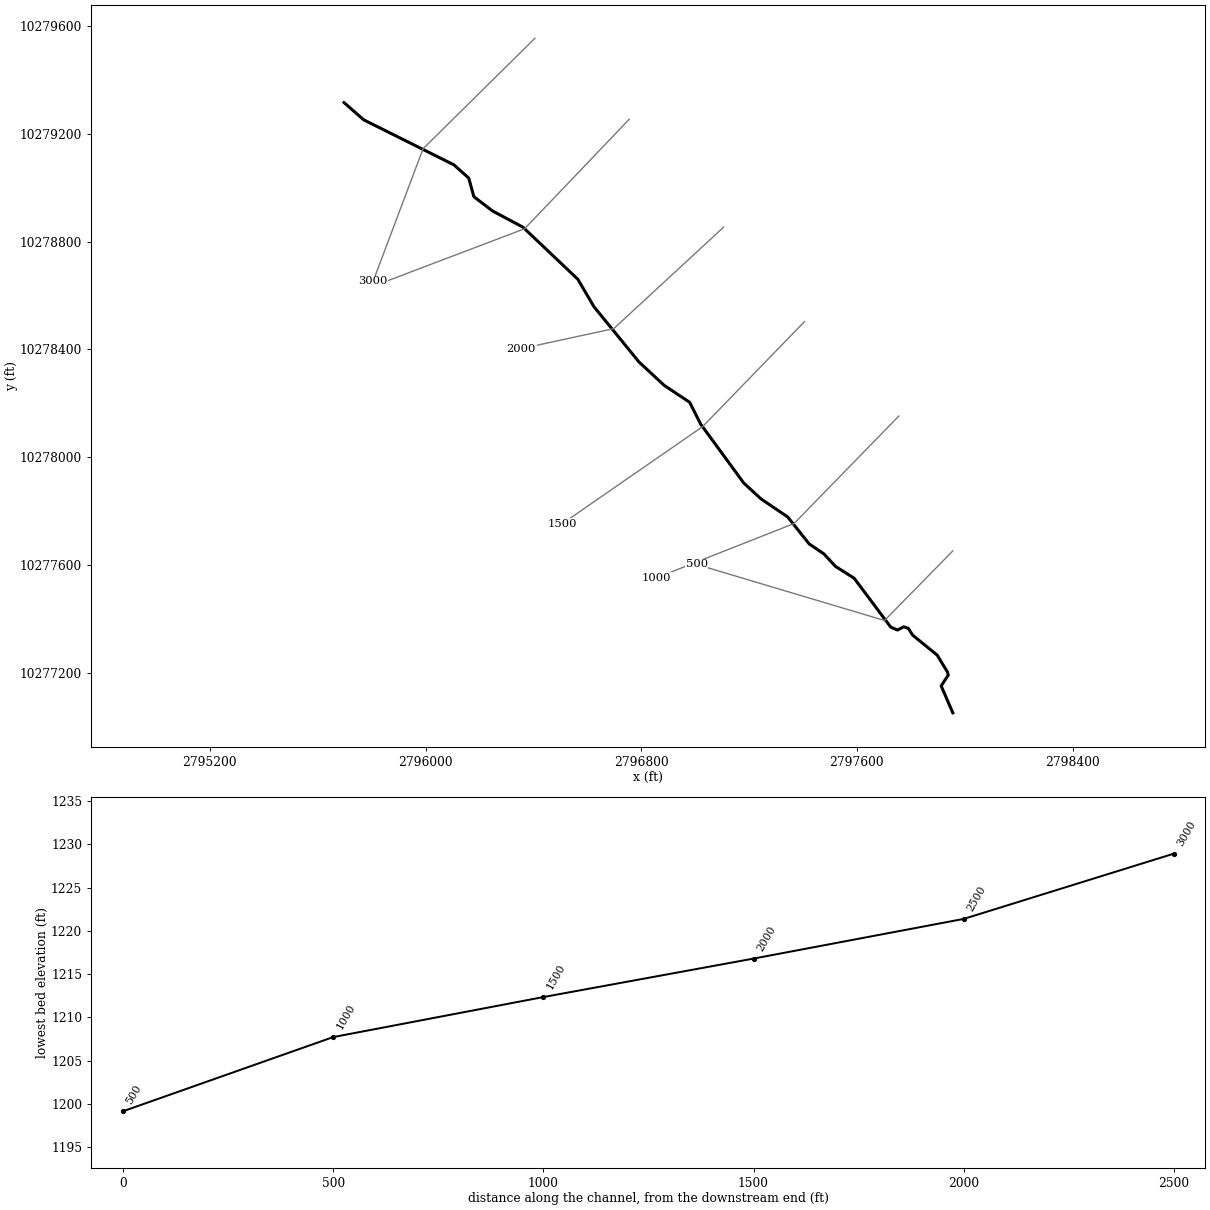
--- SANFERNANDO058.prj (project) ---

Proj Title=SANFERNANDO058 Base Level Engineering
Current Plan=p01
Default Exp/Contr=0.3,0.1
English Units
Geom File=g01
Flow File=f01
Plan File=p01
BEGIN DESCRIPTION:
SANFERNANDO058
END DESCRIPTION:

--- SANFERNANDO058.p01 (plan) ---

Plan Title=Multiple Run
Short Identifier=Multiple
Geom File=g01
Flow File=f01
Subcritical Flow
K Sum by GR= 0
Std Step Tol= 0.01
Critical Tol= 0.01
Num of Std Step Trials= 20
Max Error Tol= 0.3
Flow Tol Ratio= 0.001
Split Flow NTrial= 30
Split Flow Tol= 0.02
Split Flow Ratio= 0.02
Log Output Level= 0
Friction Slope Method= 1
Unsteady Friction Slope Method= 2
Unsteady Bridges Friction Slope Method= 1
Parabolic Critical Depth
Global Vel Dist=  1 , 1 , 1
Global Log Level= 0
CheckData=True
Encroach Param= -1, 0, 0, 0
BEGIN DESCRIPTION:
Multiple Run
END DESCRIPTION:

--- SANFERNANDO058.f01 (steady flow) ---

Flow Title=Multiple
Number of Profiles=7
Profile Names=10-year,25-year,50-year,1pct_min,100-year,1pct_plu,500-year
River Rch & RM= SANFERNANDO058,Reach-1,3000
     151     228     305     178     395     875     553
Boundary for River Rch & Prof#=SANFERNANDO058,Reach-1,1
Up Type=0
Dn Type=3
Dn Slope=0.005
Boundary for River Rch & Prof#=SANFERNANDO058,Reach-1,2
Up Type=0
Dn Type=3
Dn Slope=0.005
Boundary for River Rch & Prof#=SANFERNANDO058,Reach-1,3
Up Type=0
Dn Type=3
Dn Slope=0.005
Boundary for River Rch & Prof#=SANFERNANDO058,Reach-1,4
Up Type=0
Dn Type=3
Dn Slope=0.005
Boundary for River Rch & Prof#=SANFERNANDO058,Reach-1,5
Up Type=0
Dn Type=3
Dn Slope=0.005
Boundary for River Rch & Prof#=SANFERNANDO058,Reach-1,6
Up Type=0
Dn Type=3
Dn Slope=0.005
Boundary for River Rch & Prof#=SANFERNANDO058,Reach-1,7
Up Type=0
Dn Type=3
Dn Slope=0.005

--- SANFERNANDO058.g01 (geometry) ---

Geom Title=Existing Conditions

River Reach=SANFERNANDO058,Reach-1
Reach XY= 30
      2795697.50     10279315.00      2795770.50     10279251.00
      2796105.50     10279084.00      2796160.25     10279035.00
      2796179.25     10278966.00      2796248.75     10278913.00
      2796361.50     10278853.00      2796565.00     10278660.00
      2796624.25     10278559.00      2796791.25     10278354.00
      2796885.00     10278267.00      2796979.75     10278204.00
      2797020.75     10278123.00      2797180.25     10277905.00
      2797244.50     10277846.00      2797343.50     10277779.00
      2797423.25     10277679.00      2797478.00     10277642.00
      2797520.50     10277596.00      2797590.00     10277552.00
      2797725.50     10277371.00      2797750.50     10277360.00
      2797774.00     10277372.00      2797791.25     10277366.00
      2797807.00     10277341.00      2797898.00     10277267.00
      2797936.25     10277204.00      2797939.00     10277193.00
      2797912.75     10277153.00      2797956.00     10277053.00

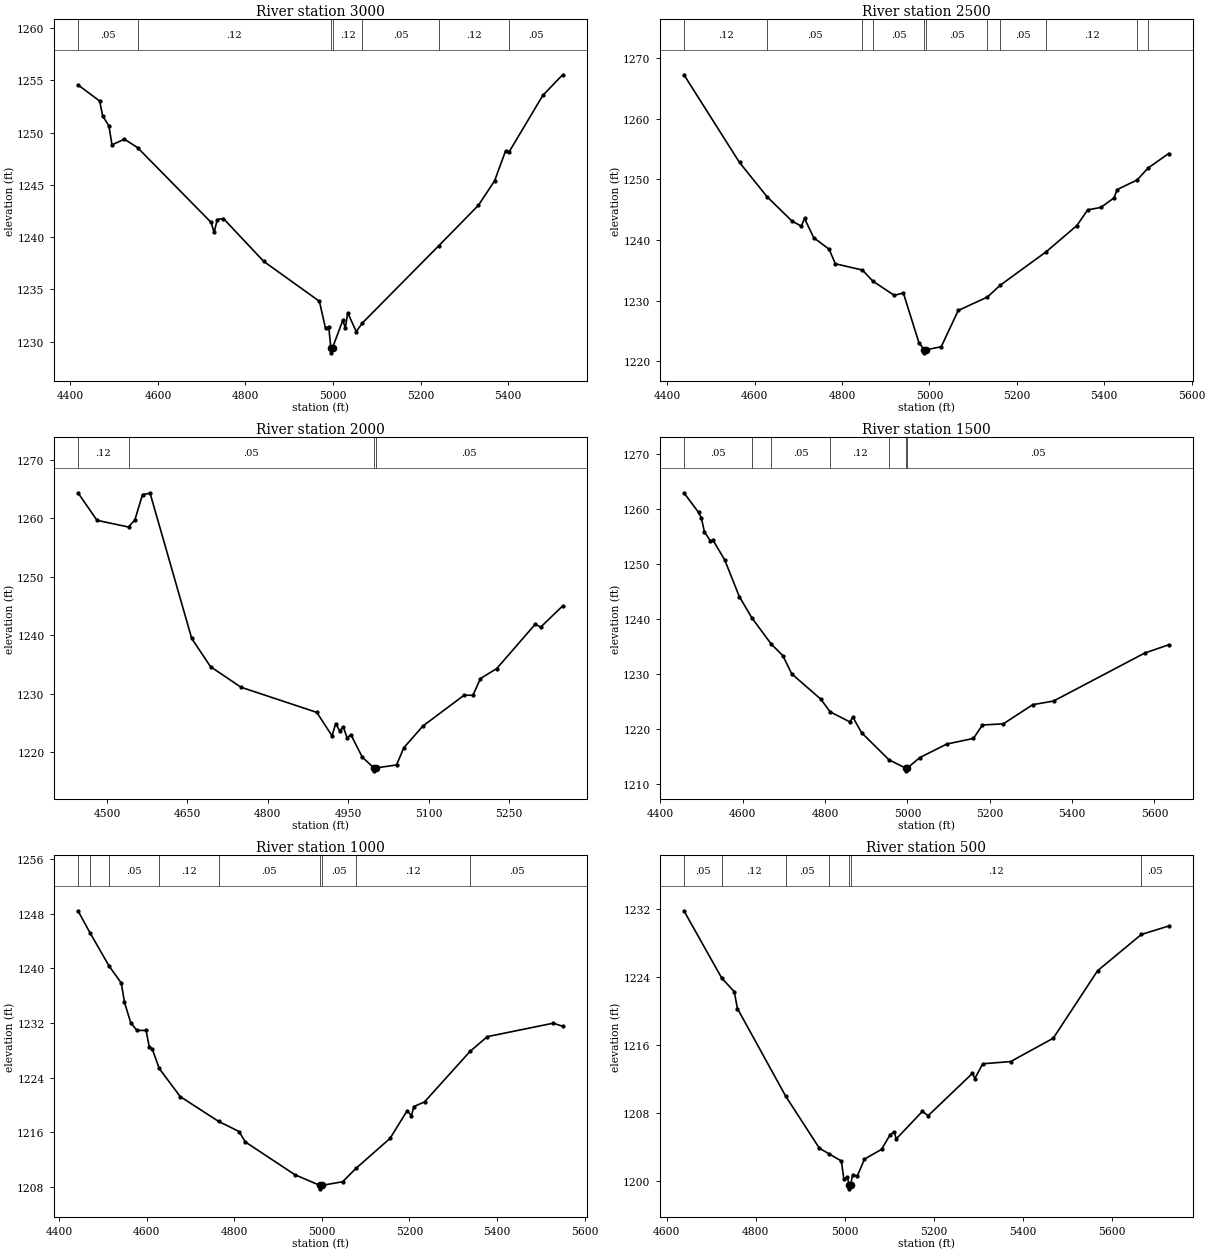
Type RM Length L Ch R = 1,3000,500,500,500
BEGIN DESCRIPTION:
SANFERNANDO058 6.0
END DESCRIPTION:
XS GIS Cut Line= 3
      2796405.65     10279553.08      2795990.89     10279143.94
      2795805.69     10278653.12
#Sta/Elev= 30
  4417.4 1254.56  4466.9 1253.01  4473.9 1251.58  4488.0 1250.64  4495.1 1248.82
  4523.4 1249.36  4553.4 1248.56  4721.4 1241.41  4728.5 1240.44  4735.6 1241.68
  4749.7 1241.77  4841.6 1237.68  4968.9 1233.86  4983.0 1231.26  4990.2 1231.44
  4995.0 1229.43  4995.3 1228.93  4999.0 1229.43  5022.3 1232.03  5028.3 1231.32
  5033.6 1232.76  5053.1 1230.96  5067.0 1231.78  5241.8 1239.18  5332.2 1243.04
  5369.2 1245.39  5394.1 1248.23  5402.8 1248.18  5479.3 1253.55  5524.6 1255.52
#Mann=7,-1,0
  4417.4    0.05       0  4553.4    0.12       0  4995.0    0.07       0
  4999.0    0.12       0  5067.0    0.05       0  5241.8    0.12       0
  5402.8    0.05       0
Bank Sta=4995,4999
Exp/Cntr=0.3,0.1

Type RM Length L Ch R = 1,2500,500,500,500
BEGIN DESCRIPTION:
SANFERNANDO058 5.0
END DESCRIPTION:
XS GIS Cut Line= 3
      2796755.66     10279253.09      2796367.43     10278847.15
      2795855.68     10278653.11
#Sta/Elev= 30
  4438.3 1267.28  4565.5 1252.80  4628.5 1247.15  4685.9 1243.11  4707.0 1242.30
  4714.2 1243.56  4735.3 1240.38  4770.5 1238.48  4784.7 1236.08  4846.6 1235.05
  4870.5 1233.22  4919.3 1230.88  4940.4 1231.25  4975.9 1223.07  4988.1 1221.88
  4988.3 1221.38  4992.1 1221.88  5027.0 1222.39  5066.0 1228.38  5132.7 1230.59
  5161.4 1232.51  5267.1 1238.06  5337.3 1242.39  5362.1 1244.98  5392.2 1245.38
  5422.3 1246.95  5429.7 1248.34  5475.2 1249.91  5500.0 1251.87  5547.3 1254.28
#Mann=11,-1,0
  4438.3    0.12       0  4628.5    0.05       0  4846.6    0.12       0
  4870.5    0.05       0  4988.1    0.05       0  4992.1    0.05       0
  5132.7    0.12       0  5161.4    0.05       0  5267.1    0.12       0
  5475.2    0.05       0  5500.0    0.12       0
Bank Sta=4988.1,4992.1
Exp/Cntr=0.3,0.1

Type RM Length L Ch R = 1,2000,500,500,500
BEGIN DESCRIPTION:
SANFERNANDO058 4.0
END DESCRIPTION:
XS GIS Cut Line= 3
      2797105.72     10278853.14      2796698.25     10278477.06
      2796355.64     10278403.10
#Sta/Elev= 30
  4445.5 1264.37  4481.0 1259.66  4540.0 1258.51  4551.9 1259.77  4566.0 1264.06
  4580.2 1264.28  4657.9 1239.44  4693.1 1234.61  4749.8 1231.10  4891.5 1226.79
  4919.9 1222.77  4926.7 1224.88  4934.1 1223.64  4940.9 1224.31  4948.2 1222.40
  4955.0 1223.00  4976.3 1219.14  4998.0 1217.29  4998.3 1216.79  5002.0 1217.29
  5040.4 1217.80  5053.8 1220.73  5089.7 1224.47  5166.3 1229.72  5183.1 1229.73
  5197.0 1232.59  5227.3 1234.28  5299.3 1241.88  5309.5 1241.38  5350.5 1245.01
#Mann=4,-1,0
  4445.5    0.12       0  4540.0    0.05       0  4998.0    0.05       0
  5002.0    0.05       0
Bank Sta=4998,5002
Exp/Cntr=0.3,0.1

Type RM Length L Ch R = 1,1500,500,500,500
BEGIN DESCRIPTION:
SANFERNANDO058 3.0
END DESCRIPTION:
XS GIS Cut Line= 3
      2797405.71     10278503.14      2797027.68     10278113.76
      2796505.66     10277753.09
#Sta/Elev= 30
  4457.3 1262.87  4492.7 1259.31  4499.7 1258.27  4506.9 1255.79  4521.0 1254.18
  4528.0 1254.23  4556.3 1250.68  4591.7 1244.02  4622.2 1240.15  4669.4 1235.37
  4697.7 1233.26  4719.1 1229.96  4789.8 1225.36  4812.3 1223.07  4860.5 1221.22
  4867.5 1222.10  4888.8 1219.27  4955.2 1214.35  4995.8 1212.84  4996.1 1212.34
  4999.8 1212.84  5030.2 1214.75  5095.7 1217.21  5160.4 1218.23  5182.3 1220.67
  5233.0 1220.88  5304.6 1224.37  5354.9 1225.02  5576.3 1233.74  5634.5 1235.24
#Mann=7,-1,0
  4457.3    0.05       0  4622.2    0.12       0  4669.4    0.05       0
  4812.3    0.12       0  4955.2    0.05       0  4995.8    0.05       0
  4999.8    0.05       0
Bank Sta=4995.8,4999.8
Exp/Cntr=0.3,0.1

Type RM Length L Ch R = 1,1000,500,500,500
BEGIN DESCRIPTION:
SANFERNANDO058 2.0
END DESCRIPTION:
XS GIS Cut Line= 3
      2797755.68     10278153.11      2797367.07     10277754.77
      2796855.70     10277553.12
#Sta/Elev= 30
  4443.5 1248.40  4470.9 1245.19  4514.2 1240.35  4542.4 1237.82  4549.6 1235.03
  4563.7 1232.05  4577.9 1230.89  4599.0 1230.89  4606.2 1228.48  4613.2 1228.15
  4628.9 1225.33  4676.9 1221.21  4764.4 1217.58  4811.2 1216.10  4825.3 1214.58
  4938.5 1209.78  4995.7 1208.21  4995.9 1207.71  4999.7 1208.21  5047.6 1208.75
  5077.7 1210.69  5155.9 1215.10  5195.0 1219.17  5204.7 1218.39  5210.0 1219.75
  5234.4 1220.43  5338.7 1227.85  5377.8 1229.98  5528.2 1231.95  5549.7 1231.50
#Mann=9,-1,0
  4443.5    0.05       0  4470.9    0.12       0  4514.2    0.05       0
  4628.9    0.12       0  4764.4    0.05       0  4995.7    0.03       0
  4999.7    0.05       0  5077.7    0.12       0  5338.7    0.05       0
Bank Sta=4995.7,4999.7
Exp/Cntr=0.3,0.1

Type RM Length L Ch R = 1,500,0,0,0
BEGIN DESCRIPTION:
SANFERNANDO058 1.0
END DESCRIPTION:
XS GIS Cut Line= 3
      2797955.65     10277653.08      2797702.63     10277395.31
      2797005.65     10277603.12
#Sta/Elev= 30
  4638.8 1231.77  4723.6 1223.88  4751.8 1222.27  4759.0 1220.29  4867.3 1210.01
  4942.8 1203.91  4964.2 1203.25  4992.3 1202.40  4998.0 1200.23  5005.9 1200.55
  5009.1 1199.63  5009.4 1199.13  5013.1 1199.63  5017.7 1200.80  5028.1 1200.64
  5044.3 1202.62  5082.7 1203.77  5101.2 1205.43  5110.6 1205.84  5115.8 1205.00
  5174.2 1208.22  5187.3 1207.72  5286.8 1212.69  5292.0 1212.08  5309.9 1213.81
  5372.5 1214.07  5468.2 1216.81  5567.7 1224.73  5666.0 1228.99  5727.3 1229.98
#Mann=7,-1,0
  4638.8    0.05       0  4723.6    0.12       0  4867.3    0.05       0
  4964.2    0.12       0  5009.1    0.07       0  5013.1    0.12       0
  5666.0    0.05       0
Bank Sta=5009.1,5013.1
Exp/Cntr=0.3,0.1

Chan Stop Cuts=-1