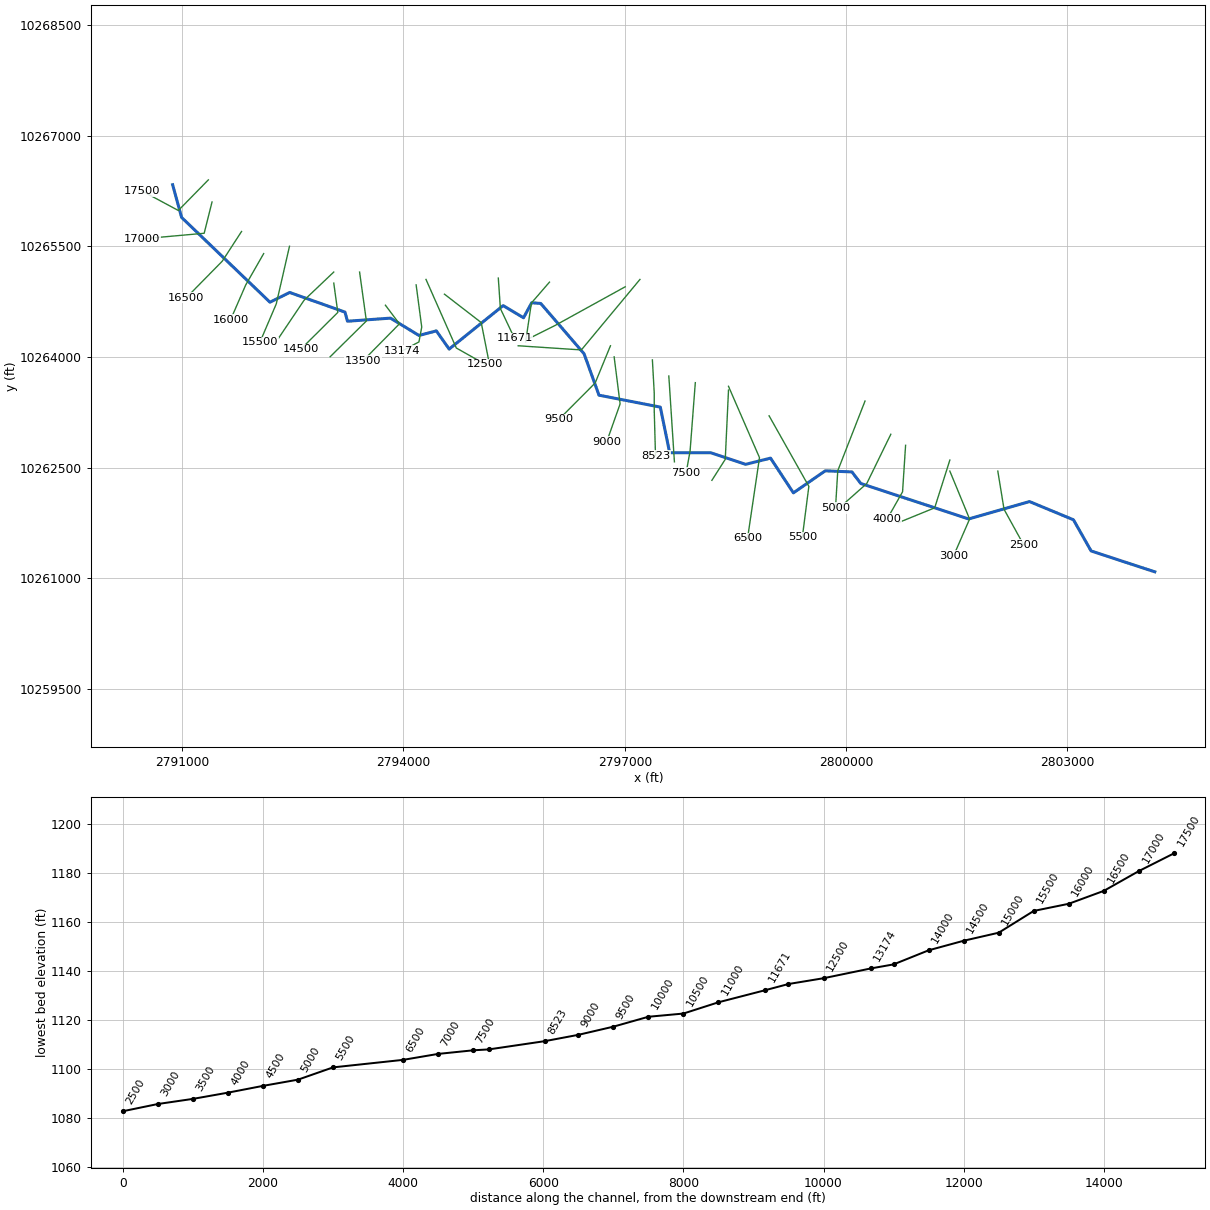
--- SANFERNANDO059.prj (project) ---

Proj Title=SANFERNANDO059 Base Level Engineering
Current Plan=p01
Default Exp/Contr=0.3,0.1
English Units
Geom File=g01
Flow File=f01
Plan File=p01
BEGIN DESCRIPTION:
SANFERNANDO059
END DESCRIPTION:

--- SANFERNANDO059.p01 (plan) ---

Plan Title=Multiple Run
Short Identifier=Multiple
Geom File=g01
Flow File=f01
Subcritical Flow
K Sum by GR= 0
Std Step Tol= 0.01
Critical Tol= 0.01
Num of Std Step Trials= 20
Max Error Tol= 0.3
Flow Tol Ratio= 0.001
Split Flow NTrial= 30
Split Flow Tol= 0.02
Split Flow Ratio= 0.02
Log Output Level= 0
Friction Slope Method= 1
Unsteady Friction Slope Method= 2
Unsteady Bridges Friction Slope Method= 1
Parabolic Critical Depth
Global Vel Dist=  1 , 1 , 1
Global Log Level= 0
CheckData=True
Encroach Param= -1, 0, 0, 0
BEGIN DESCRIPTION:
Multiple Run
END DESCRIPTION:

--- SANFERNANDO059.f01 (steady flow) ---

Flow Title=Multiple
Number of Profiles=7
Profile Names=10-year,25-year,50-year,1pct_min,100-year,1pct_plu,500-year
River Rch & RM= SANFERNANDO059,Reach-1,17500
     392     627     778     457    1020    2278    1380
River Rch & RM= SANFERNANDO059,Reach-1,10500
     550     904    1063     691    1404    2852    1892
River Rch & RM= SANFERNANDO059,Reach-1,6500
     663    1100    1350     811    1796    3977    2414
River Rch & RM= SANFERNANDO059,Reach-1,5500
     775    1300    1605    1037    2148    4450    2887
River Rch & RM= SANFERNANDO059,Reach-1,3500
     991    1692    2110    1219    2848    6656    3828
Boundary for River Rch & Prof#=SANFERNANDO059,Reach-1,1
Up Type=0
Dn Type=3
Dn Slope=0.005
Boundary for River Rch & Prof#=SANFERNANDO059,Reach-1,2
Up Type=0
Dn Type=3
Dn Slope=0.005
Boundary for River Rch & Prof#=SANFERNANDO059,Reach-1,3
Up Type=0
Dn Type=3
Dn Slope=0.005
Boundary for River Rch & Prof#=SANFERNANDO059,Reach-1,4
Up Type=0
Dn Type=3
Dn Slope=0.005
Boundary for River Rch & Prof#=SANFERNANDO059,Reach-1,5
Up Type=0
Dn Type=3
Dn Slope=0.005
Boundary for River Rch & Prof#=SANFERNANDO059,Reach-1,6
Up Type=0
Dn Type=3
Dn Slope=0.005
Boundary for River Rch & Prof#=SANFERNANDO059,Reach-1,7
Up Type=0
Dn Type=3
Dn Slope=0.005

--- SANFERNANDO059.g01 (geometry) ---

Geom Title=Existing Conditions

River Reach=SANFERNANDO059,Reach-1
Reach XY= 30
      2790872.00     10266337.00      2790993.25     10265894.00
      2792190.75     10264744.00      2792458.25     10264876.00
      2793207.25     10264610.00      2793241.50     10264486.00
      2793824.00     10264528.00      2794210.75     10264293.00
      2794446.00     10264355.00      2794619.50     10264108.00
      2795351.25     10264698.00      2795627.25     10264533.00
      2795738.50     10264737.00      2795861.25     10264727.00
      2796448.50     10264044.00      2796650.00     10263483.00
      2797481.50     10263321.00      2797608.25     10262702.00
      2798165.50     10262702.00      2798637.75     10262545.00
      2798975.50     10262629.00      2799285.25     10262158.00
      2799716.75     10262457.00      2800078.75     10262442.00
      2800198.50     10262285.00      2801660.50     10261804.00
      2802485.25     10262040.00      2803080.75     10261793.00
      2803320.25     10261370.00      2804183.00     10261087.00

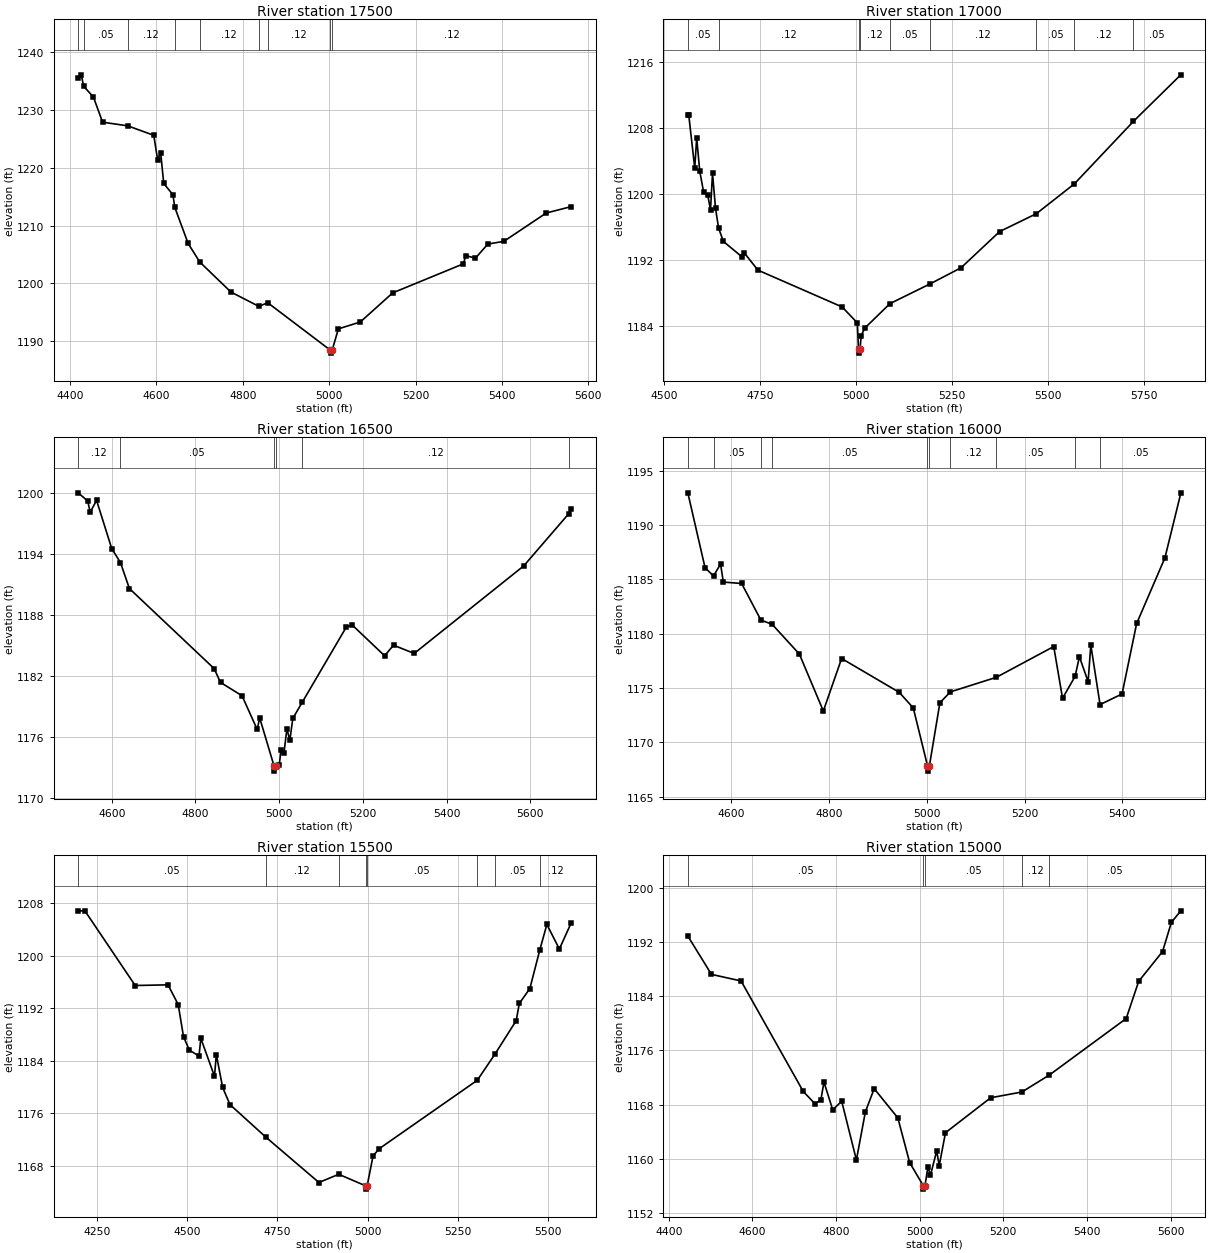
Type RM Length L Ch R = 1,17500,500,500,500
BEGIN DESCRIPTION:
SANFERNANDO059 35.0
END DESCRIPTION:
XS GIS Cut Line= 3
      2791355.70     10266403.13      2790949.10     10265987.97
      2790455.72     10266253.09
#Sta/Elev= 30
  4418.9 1235.54  4426.0 1236.10  4431.5 1234.14  4454.3 1232.23  4475.4 1227.90
  4533.5 1227.27  4593.9 1225.63  4602.7 1221.42  4609.9 1222.57  4616.9 1217.30
  4638.2 1215.34  4642.6 1213.15  4673.4 1206.91  4700.4 1203.69  4772.5 1198.50
  4837.3 1196.01  4857.6 1196.65  5002.9 1188.42  5003.2 1187.92  5006.9 1188.42
  5021.2 1192.12  5072.0 1193.31  5147.0 1198.35  5310.4 1203.37  5316.6 1204.81
  5338.5 1204.35  5367.2 1206.80  5404.3 1207.27  5502.5 1212.18  5560.1 1213.28
#Mann=9,-1,0
  4418.9    0.12       0  4431.5    0.05       0  4533.5    0.12       0
  4642.6    0.05       0  4700.4    0.12       0  4837.3    0.05       0
  4857.6    0.12       0  5002.9    0.07       0  5006.9    0.12       0
Bank Sta=5002.9,5006.9
Exp/Cntr=0.3,0.1

Type RM Length L Ch R = 1,17000,500,500,500
BEGIN DESCRIPTION:
SANFERNANDO059 34.0
END DESCRIPTION:
XS GIS Cut Line= 3
      2791405.67     10266103.07      2791299.21     10265679.03
      2790455.72     10265603.11
#Sta/Elev= 30
  4562.8 1209.56  4565.3 1209.56  4580.8 1203.18  4585.9 1206.82  4593.7 1202.84
  4604.0 1200.22  4614.3 1199.95  4621.9 1198.11  4627.1 1202.52  4634.9 1198.30
  4642.9 1195.88  4655.5 1194.26  4704.2 1192.38  4709.4 1192.90  4745.4 1190.78
  4964.9 1186.31  5004.3 1184.38  5007.4 1181.21  5007.6 1180.71  5011.4 1181.21
  5014.4 1182.82  5023.6 1183.74  5089.4 1186.72  5194.2 1189.12  5274.6 1191.07
  5375.0 1195.46  5470.7 1197.63  5569.5 1201.24  5723.5 1208.83  5846.9 1214.48
#Mann=9,-1,0
  4562.8    0.05       0  4642.9    0.12       0  5007.4    0.07       0
  5011.4    0.12       0  5089.4    0.05       0  5194.2    0.12       0
  5470.7    0.05       0  5569.5    0.12       0  5723.5    0.05       0
Bank Sta=5007.4,5011.4
Exp/Cntr=0.3,0.1

Type RM Length L Ch R = 1,16500,500,500,500
BEGIN DESCRIPTION:
SANFERNANDO059 33.0
END DESCRIPTION:
XS GIS Cut Line= 3
      2791805.70     10265703.13      2791544.48     10265300.32
      2791055.71     10264803.13
#Sta/Elev= 30
  4519.9 1199.99  4542.6 1199.19  4548.6 1198.09  4563.8 1199.25  4600.0 1194.51
  4620.9 1193.13  4642.2 1190.58  4844.6 1182.71  4859.8 1181.35  4911.2 1180.04
  4947.4 1176.73  4953.4 1177.86  4987.7 1173.13  4987.9 1172.63  4991.7 1173.13
  5000.0 1173.22  5004.3 1174.67  5011.3 1174.40  5018.4 1176.79  5025.4 1175.66
  5032.5 1177.81  5055.0 1179.40  5159.8 1186.76  5174.0 1187.01  5251.7 1183.97
  5273.0 1185.01  5322.4 1184.20  5584.1 1192.81  5691.6 1197.94  5697.2 1198.43
#Mann=6,-1,0
  4519.9    0.12       0  4620.9    0.05       0  4987.7    0.05       0
  4991.7    0.05       0  5055.0    0.12       0  5691.6    0.05       0
Bank Sta=4987.7,4991.7
Exp/Cntr=0.3,0.1

Type RM Length L Ch R = 1,16000,500,500,500
BEGIN DESCRIPTION:
SANFERNANDO059 32.0
END DESCRIPTION:
XS GIS Cut Line= 3
      2792105.67     10265403.08      2791862.99     10264979.24
      2791655.68     10264503.11
#Sta/Elev= 30
  4511.6 1192.96  4546.8 1186.07  4564.1 1185.31  4578.5 1186.41  4584.2 1184.75
  4621.6 1184.62  4661.0 1181.25  4683.8 1180.87  4739.6 1178.13  4788.6 1172.89
  4826.0 1177.72  4944.0 1174.60  4972.5 1173.17  5001.5 1167.86  5001.8 1167.36
  5005.5 1167.86  5026.9 1173.65  5048.4 1174.65  5142.3 1175.99  5259.6 1178.82
  5277.6 1174.06  5303.3 1176.08  5312.1 1177.88  5329.9 1175.59  5335.4 1178.96
  5354.3 1173.48  5399.3 1174.46  5429.1 1180.94  5486.9 1186.98  5519.3 1192.91
#Mann=10,-1,0
  4511.6    0.12       0  4564.1    0.05       0  4661.0    0.12       0
  4683.8    0.05       0  5001.5    0.05       0  5005.5    0.05       0
  5048.4    0.12       0  5142.3    0.05       0  5303.3    0.12       0
  5354.3    0.05       0
Bank Sta=5001.5,5005.5
Exp/Cntr=0.3,0.1

Type RM Length L Ch R = 1,15500,500,500,500
BEGIN DESCRIPTION:
SANFERNANDO059 31.0
END DESCRIPTION:
XS GIS Cut Line= 3
      2792455.68     10265503.10      2792276.66     10264721.74
      2792055.70     10264203.15
#Sta/Elev= 30
  4198.4 1206.85  4217.3 1206.82  4356.3 1195.47  4447.2 1195.57  4475.4 1192.57
  4490.1 1187.68  4506.2 1185.63  4533.0 1184.71  4538.1 1187.41  4575.9 1181.64
  4581.0 1184.94  4598.5 1179.94  4618.8 1177.32  4717.6 1172.39  4865.2 1165.45
  4920.0 1166.70  4994.7 1164.94  4995.0 1164.44  4998.7 1164.94  5015.0 1169.47
  5031.1 1170.56  5303.8 1181.03  5353.2 1185.05  5411.6 1190.12  5420.2 1192.74
  5449.3 1194.99  5477.0 1200.90  5496.5 1204.77  5531.1 1201.03  5563.7 1204.99
#Mann=8,-1,0
  4198.4    0.05       0  4717.6    0.12       0  4920.0    0.05       0
  4994.7    0.05       0  4998.7    0.05       0  5303.8    0.12       0
  5353.2    0.05       0  5477.0    0.12       0
Bank Sta=4994.7,4998.7
Exp/Cntr=0.3,0.1

Type RM Length L Ch R = 1,15000,500,500,500
BEGIN DESCRIPTION:
SANFERNANDO059 30.0
END DESCRIPTION:
XS GIS Cut Line= 3
      2793055.72     10265153.14      2792653.70     10264771.24
      2792305.66     10264253.08
#Sta/Elev= 30
  4445.5 1192.86  4502.0 1187.21  4572.8 1186.24  4721.4 1169.96  4749.5 1168.13
  4763.7 1168.71  4771.0 1171.34  4792.0 1167.24  4813.4 1168.51  4848.6 1159.84
  4870.0 1166.94  4891.1 1170.36  4947.7 1166.05  4976.0 1159.45  5008.6 1156.05
  5008.9 1155.55  5012.6 1156.05  5019.6 1158.85  5025.6 1157.58  5040.6 1161.19
  5046.6 1159.01  5061.6 1163.87  5169.6 1169.02  5244.3 1169.87  5310.1 1172.38
  5493.7 1180.70  5523.6 1186.19  5580.7 1190.58  5601.7 1194.87  5624.2 1196.58
#Mann=5,-1,0
  4445.5    0.05       0  5008.6    0.05       0  5012.6    0.05       0
  5244.3    0.12       0  5310.1    0.05       0
Bank Sta=5008.6,5012.6
Exp/Cntr=0.3,0.1

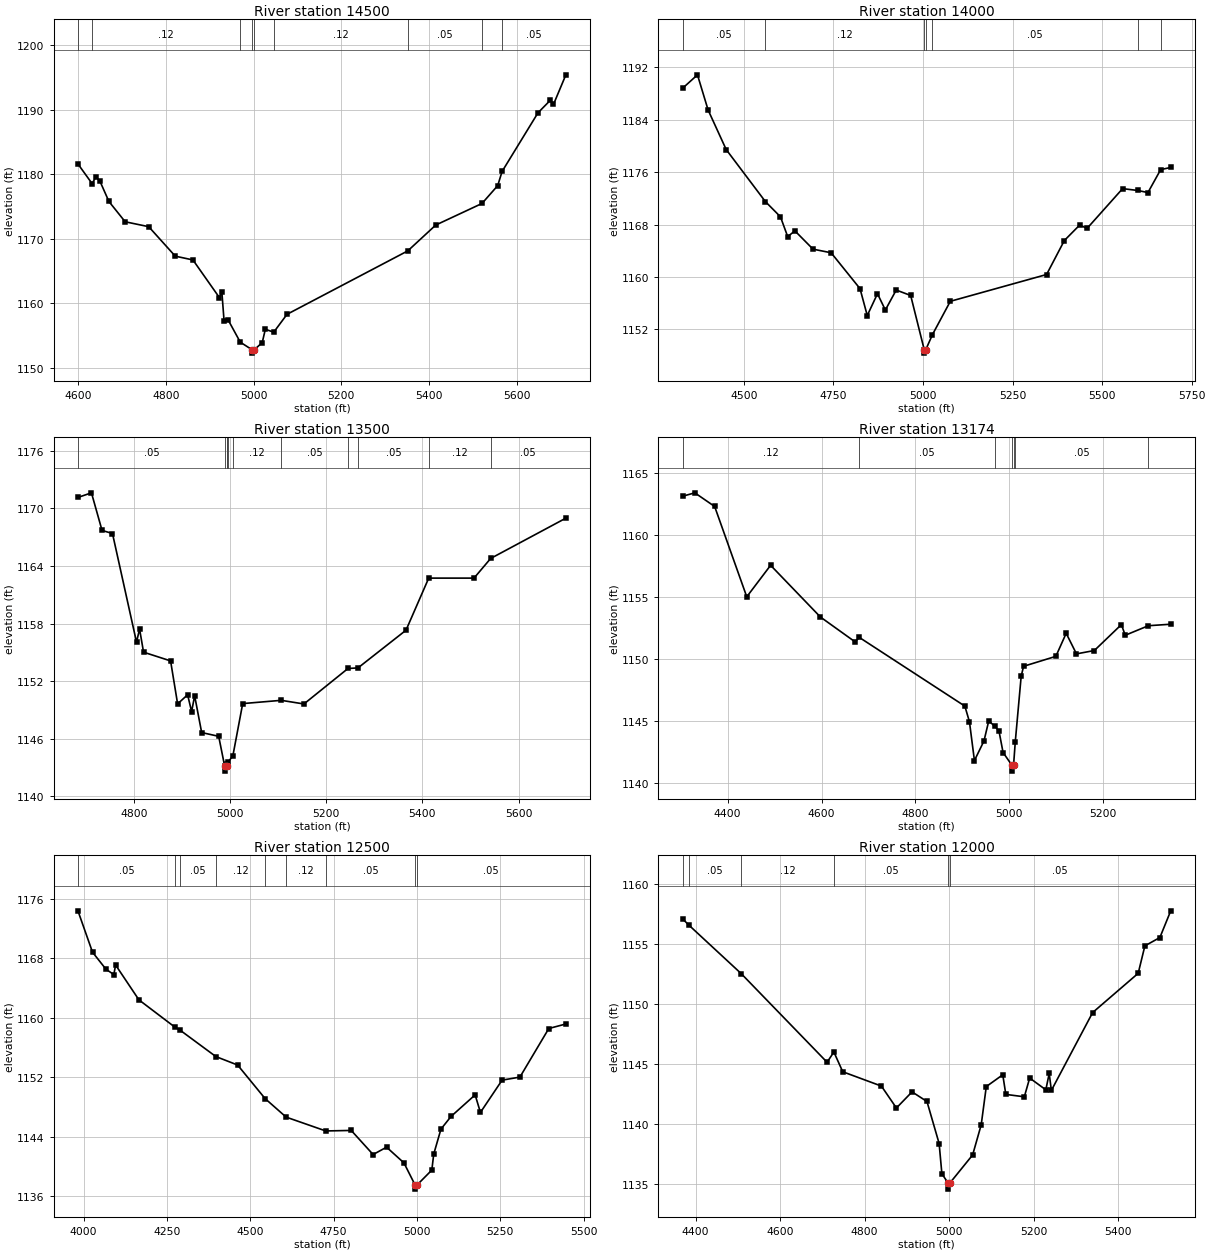
Type RM Length L Ch R = 1,14500,500,500,500
BEGIN DESCRIPTION:
SANFERNANDO059 29.0
END DESCRIPTION:
XS GIS Cut Line= 3
      2793055.68     10265003.11      2793110.60     10264605.69
      2792605.69     10264103.11
#Sta/Elev= 30
  4598.8 1181.61  4631.1 1178.56  4639.8 1179.58  4649.3 1178.89  4669.5 1175.79
  4706.6 1172.64  4760.3 1171.88  4820.9 1167.31  4861.3 1166.72  4921.8 1160.87
  4927.2 1161.81  4932.3 1157.28  4942.0 1157.37  4969.3 1153.97  4996.8 1152.77
  4997.0 1152.27  5000.8 1152.77  5019.4 1153.90  5026.5 1155.97  5045.7 1155.52
  5076.0 1158.29  5351.7 1168.13  5415.4 1172.13  5521.0 1175.48  5556.9 1178.25
  5566.8 1180.44  5648.8 1189.54  5677.0 1191.49  5684.1 1190.83  5712.4 1195.43
#Mann=9,-1,0
  4598.8    0.05       0  4631.1    0.12       0  4969.3    0.05       0
  4996.8    0.05       0  5000.8    0.05       0  5045.7    0.12       0
  5351.7    0.05       0  5521.0    0.12       0  5566.8    0.05       0
Bank Sta=4996.8,5000.8
Exp/Cntr=0.3,0.1

Type RM Length L Ch R = 1,14000,500,500,500
BEGIN DESCRIPTION:
SANFERNANDO059 28.0
END DESCRIPTION:
XS GIS Cut Line= 3
      2793405.69     10265153.07      2793497.67     10264489.21
      2793005.70     10264003.13
#Sta/Elev= 30
  4329.8 1188.83  4370.7 1190.85  4400.4 1185.48  4450.9 1179.44  4560.3 1171.50
  4602.3 1169.18  4622.5 1166.16  4642.7 1167.03  4693.2 1164.24  4743.7 1163.69
  4824.4 1158.21  4844.6 1154.11  4873.1 1157.44  4895.1 1154.95  4925.4 1158.00
  4965.8 1157.17  5003.7 1148.87  5003.9 1148.37  5007.7 1148.87  5026.5 1151.19
  5076.4 1156.28  5345.1 1160.37  5394.7 1165.56  5437.1 1167.90  5458.3 1167.42
  5557.3 1173.48  5599.2 1173.20  5628.0 1172.88  5663.5 1176.38  5691.6 1176.71
#Mann=7,-1,0
  4329.8    0.05       0  4560.3    0.12       0  5003.7    0.07       0
  5007.7    0.12       0  5026.5    0.05       0  5599.2    0.12       0
  5663.5    0.05       0
Bank Sta=5003.7,5007.7
Exp/Cntr=0.3,0.1

Type RM Length L Ch R = 1,13500,326,326,326
BEGIN DESCRIPTION:
SANFERNANDO059 27.0
END DESCRIPTION:
XS GIS Cut Line= 3
      2793755.68     10264703.12      2793945.72     10264450.65
      2793455.71     10263953.14
#Sta/Elev= 30
  4684.0 1171.15  4712.1 1171.63  4734.1 1167.71  4755.8 1167.39  4805.8 1156.06
  4812.1 1157.44  4820.4 1155.02  4876.6 1154.11  4891.2 1149.63  4912.0 1150.58
  4920.3 1148.82  4926.6 1150.48  4941.2 1146.64  4976.6 1146.25  4989.1 1143.12
  4989.4 1142.62  4993.1 1143.12  4994.6 1143.36  4995.9 1143.55  5006.1 1144.22
  5026.5 1149.66  5106.7 1150.00  5153.8 1149.62  5245.4 1153.32  5266.2 1153.38
  5366.0 1157.31  5413.2 1162.74  5507.4 1162.74  5542.0 1164.79  5698.3 1168.99
#Mann=11,-1,0
  4684.0    0.05       0  4989.1    0.05       0  4993.1    0.05       0
  4994.6    0.12       0  4995.9    0.05       0  5006.1    0.12       0
  5106.7    0.05       0  5245.4    0.12       0  5266.2    0.05       0
  5413.2    0.12       0  5542.0    0.05       0
Bank Sta=4989.1,4993.1
Exp/Cntr=0.3,0.1

Type RM Length L Ch R = 1,13174,674,674,674
BEGIN DESCRIPTION:
Mapping XS 0f568af6
END DESCRIPTION:
XS GIS Cut Line= 4
      2794172.20     10264978.46      2794247.83     10264407.01
      2794210.01     10264205.31      2793983.11     10264083.45
#Sta/Elev= 30
  4304.6 1163.12  4330.2 1163.39  4372.4 1162.29  4440.8 1155.01  4491.6 1157.55
  4597.7 1153.38  4671.1 1151.39  4680.8 1151.73  4905.3 1146.20  4915.1 1144.94
  4925.7 1141.81  4946.0 1143.39  4956.2 1145.01  4968.6 1144.59  4977.9 1144.21
  4986.7 1142.46  5005.1 1141.46  5005.3 1140.96  5009.1 1141.46  5012.7 1143.33
  5025.3 1148.62  5030.4 1149.41  5099.1 1150.21  5121.1 1152.07  5143.0 1150.41
  5181.1 1150.68  5238.7 1152.77  5246.9 1151.91  5296.2 1152.68  5343.8 1152.80
#Mann=7,-1,0
  4304.6    0.12       0  4680.8    0.05       0  4968.6    0.12       0
  5005.1    0.07       0  5009.1    0.12       0  5012.7    0.05       0
  5296.2    0.12       0
Bank Sta=5005.1,5009.1
Exp/Cntr=0.3,0.1

Type RM Length L Ch R = 1,12500,500,500,500
BEGIN DESCRIPTION:
SANFERNANDO059 25.0
END DESCRIPTION:
XS GIS Cut Line= 3
      2794305.69     10265053.09      2794716.59     10264122.79
      2795105.66     10263903.13
#Sta/Elev= 30
  3983.0 1174.38  4026.7 1168.82  4067.3 1166.52  4090.6 1165.82  4096.1 1167.09
  4166.0 1162.41  4273.4 1158.76  4288.5 1158.37  4396.8 1154.79  4462.1 1153.65
  4544.5 1149.14  4607.6 1146.65  4726.5 1144.79  4802.9 1144.86  4868.5 1141.62
  4908.9 1142.61  4961.0 1140.50  4995.1 1137.47  4995.3 1136.97  4999.1 1137.47
  5044.7 1139.53  5050.4 1141.68  5072.1 1145.04  5102.3 1146.74  5174.6 1149.64
  5190.5 1147.28  5255.5 1151.62  5309.0 1152.03  5395.6 1158.56  5446.8 1159.17
#Mann=9,-1,0
  3983.0    0.05       0  4273.4    0.12       0  4288.5    0.05       0
  4396.8    0.12       0  4544.5    0.05       0  4607.6    0.12       0
  4726.5    0.05       0  4995.1    0.05       0  4999.1    0.05       0
Bank Sta=4995.1,4999.1
Exp/Cntr=0.3,0.1

Type RM Length L Ch R = 1,12000,329,329,329
BEGIN DESCRIPTION:
SANFERNANDO059 24.0
END DESCRIPTION:
XS GIS Cut Line= 3
      2794555.70     10264853.10      2795054.33     10264467.72
      2795155.69     10263953.10
#Sta/Elev= 30
  4369.8 1157.05  4383.3 1156.57  4507.8 1152.52  4711.2 1145.15  4727.3 1146.00
  4748.3 1144.36  4839.8 1143.17  4875.3 1141.35  4912.3 1142.69  4947.6 1141.89
  4976.4 1138.40  4982.9 1135.89  4997.7 1135.11  4997.9 1134.61  5001.7 1135.11
  5055.7 1137.45  5076.0 1139.96  5088.0 1143.13  5127.0 1144.11  5134.2 1142.48
  5178.0 1142.28  5190.7 1143.84  5228.9 1142.86  5236.9 1144.22  5242.0 1142.81
  5339.7 1149.28  5447.5 1152.54  5463.3 1154.82  5498.8 1155.51  5524.5 1157.73
#Mann=6,-1,0
  4369.8    0.12       0  4383.3    0.05       0  4507.8    0.12       0
  4727.3    0.05       0  4997.7    0.05       0  5001.7    0.05       0
Bank Sta=4997.7,5001.7
Exp/Cntr=0.3,0.1

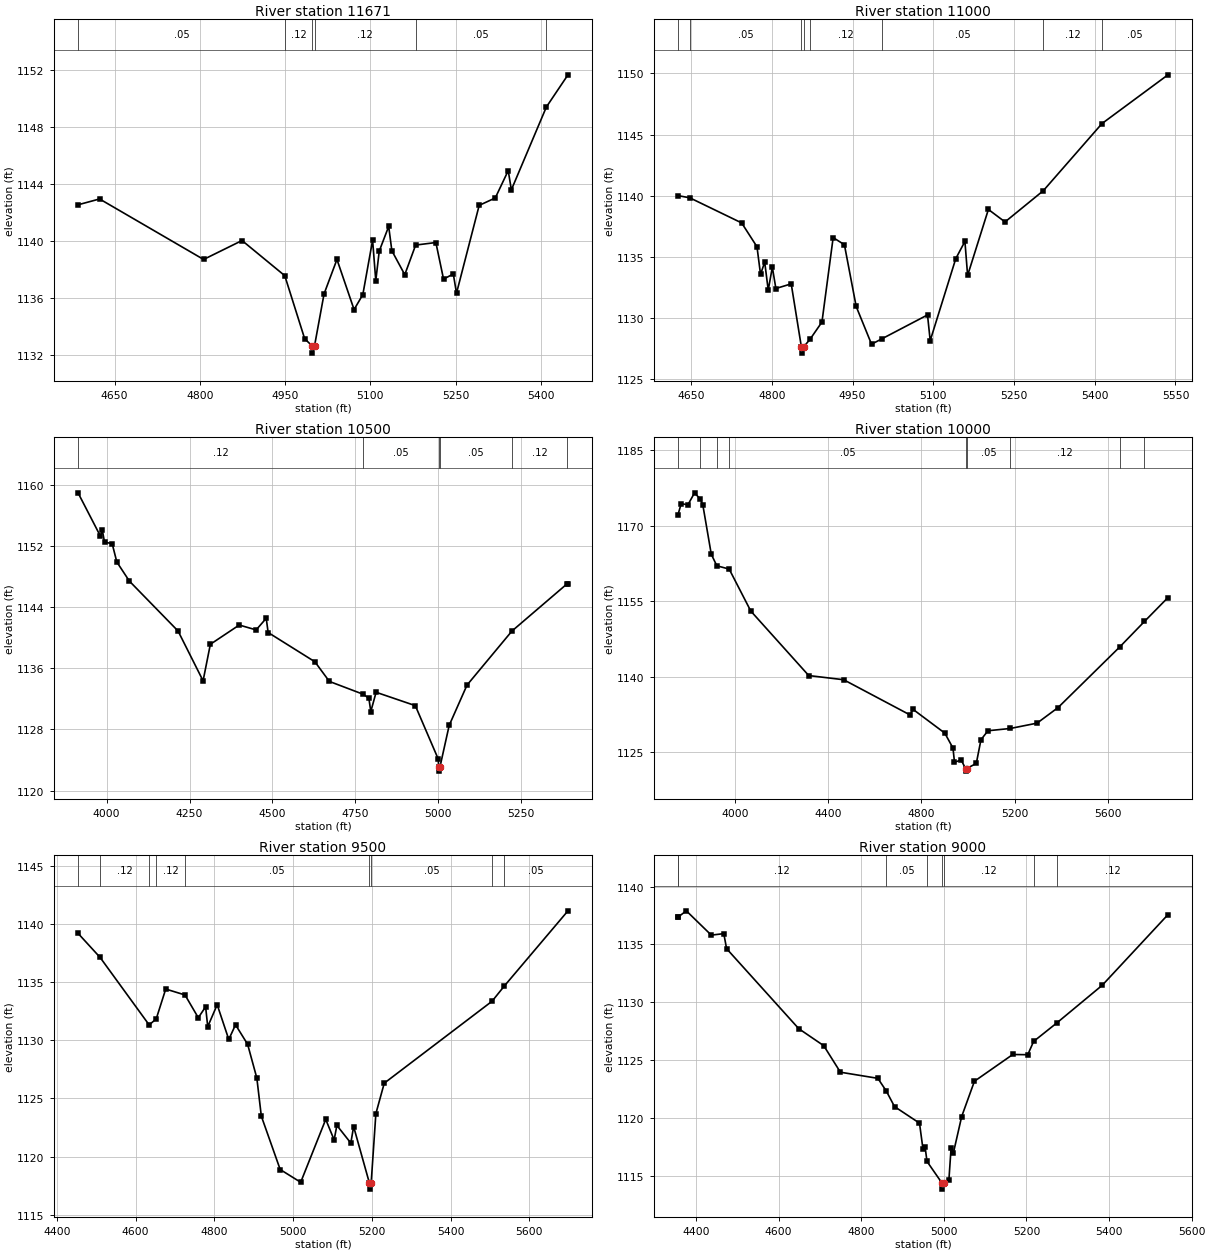
Type RM Length L Ch R = 1,11671,671,671,671
BEGIN DESCRIPTION:
SANFERNANDO059 23.0
END DESCRIPTION:
XS GIS Cut Line= 3
      2795285.74     10265070.92      2795314.07     10264657.59
      2795505.70     10264253.08
#Sta/Elev= 30
  4585.7 1142.53  4623.6 1142.94  4806.6 1138.69  4874.2 1140.02  4949.4 1137.55
  4984.4 1133.12  4997.7 1132.61  4998.0 1132.11  5001.7 1132.61  5018.5 1136.27
  5041.2 1138.69  5071.3 1135.17  5086.7 1136.22  5103.9 1140.04  5109.5 1137.20
  5115.6 1139.28  5132.2 1141.01  5137.8 1139.30  5160.5 1137.62  5179.6 1139.70
  5215.2 1139.88  5228.7 1137.31  5245.9 1137.67  5251.5 1136.32  5291.4 1142.49
  5319.7 1143.01  5342.5 1144.93  5348.0 1143.58  5409.6 1149.40  5447.6 1151.66
#Mann=6,-1,0
  4585.7    0.05       0  4949.4    0.12       0  4997.7    0.07       0
  5001.7    0.12       0  5179.6    0.05       0  5409.6    0.12       0
Bank Sta=4997.7,5001.7
Exp/Cntr=0.3,0.1

Type RM Length L Ch R = 1,11000,500,500,500
BEGIN DESCRIPTION:
SANFERNANDO059 22.0
END DESCRIPTION:
XS GIS Cut Line= 3
      2795979.08     10265016.31      2795734.22     10264733.33
      2795655.69     10264203.12
#Sta/Elev= 30
  4625.8 1140.02  4647.7 1139.84  4744.0 1137.79  4772.5 1135.84  4779.1 1133.58
  4786.8 1134.59  4793.4 1132.30  4801.0 1134.17  4807.6 1132.43  4836.1 1132.81
  4855.0 1127.65  4855.3 1127.15  4859.0 1127.65  4871.2 1128.29  4893.2 1129.69
  4914.0 1136.59  4934.9 1136.01  4956.8 1130.96  4985.3 1127.88  5004.6 1128.32
  5089.3 1130.27  5094.3 1128.17  5141.8 1134.87  5158.8 1136.28  5163.8 1133.50
  5202.4 1138.89  5233.3 1137.87  5304.4 1140.42  5413.5 1145.91  5536.0 1149.89
#Mann=8,-1,0
  4625.8    0.12       0  4647.7    0.05       0  4855.0    0.07       0
  4859.0    0.05       0  4871.2    0.12       0  5004.6    0.05       0
  5304.4    0.12       0  5413.5    0.05       0
Bank Sta=4855,4859
Exp/Cntr=0.3,0.1

Type RM Length L Ch R = 1,10500,500,500,500
BEGIN DESCRIPTION:
SANFERNANDO059 21.0
END DESCRIPTION:
XS GIS Cut Line= 3
      2797005.68     10264953.11      2796054.88     10264428.34
      2795705.68     10264253.11
#Sta/Elev= 30
  3914.0 1158.97  3981.6 1153.29  3987.3 1154.04  3993.9 1152.51  4016.8 1152.33
  4030.9 1149.92  4068.7 1147.42  4215.4 1140.89  4290.9 1134.37  4312.8 1139.15
  4399.9 1141.67  4450.8 1141.03  4481.2 1142.55  4487.0 1140.69  4627.9 1136.86
  4671.5 1134.29  4774.0 1132.60  4790.6 1132.09  4796.4 1130.35  4812.4 1132.87
  4930.6 1131.12  5000.0 1124.10  5000.5 1123.05  5000.8 1122.55  5004.6 1123.05
  5032.7 1128.54  5086.4 1133.81  5221.8 1140.88  5389.1 1147.10  5390.7 1147.10
#Mann=6,-1,0
  3914.0    0.12       0  4774.0    0.05       0  5000.5    0.05       0
  5004.6    0.05       0  5221.8    0.12       0  5389.1    0.05       0
Bank Sta=5000.5,5004.6
Exp/Cntr=0.3,0.1

Type RM Length L Ch R = 1,10000,500,500,500
BEGIN DESCRIPTION:
SANFERNANDO059 20.0
END DESCRIPTION:
XS GIS Cut Line= 3
      2797205.67     10265053.10      2796411.20     10264096.61
      2795555.67     10264153.11
#Sta/Elev= 30
  3756.6 1172.18  3770.2 1174.36  3798.9 1174.13  3827.5 1176.51  3852.5 1175.23
  3862.7 1174.18  3899.2 1164.31  3923.0 1162.02  3975.9 1161.37  4068.6 1153.03
  4317.1 1140.22  4466.9 1139.39  4750.7 1132.42  4765.1 1133.48  4900.5 1128.79
  4935.6 1125.82  4942.1 1123.00  4970.8 1123.46  4989.5 1121.74  4989.8 1121.24
  4993.7 1121.74  5035.6 1122.77  5055.6 1127.48  5085.7 1129.26  5181.2 1129.71
  5296.2 1130.77  5386.4 1133.87  5651.3 1145.93  5756.8 1150.97  5857.4 1155.71
#Mann=9,-1,0
  3756.6    0.12       0  3852.5    0.05       0  3923.0    0.12       0
  3975.9    0.05       0  4989.5    0.03       0  4993.7    0.05       0
  5181.2    0.12       0  5651.3    0.05       0  5756.8    0.12       0
Bank Sta=4989.5,4993.7
Exp/Cntr=0.3,0.1

Type RM Length L Ch R = 1,9500,500,500,500
BEGIN DESCRIPTION:
SANFERNANDO059 19.0
END DESCRIPTION:
XS GIS Cut Line= 3
      2796805.70     10264153.15      2796598.19     10263647.91
      2796105.71     10263153.13
#Sta/Elev= 30
  4453.8 1139.23  4509.7 1137.16  4634.4 1131.34  4652.4 1131.86  4676.5 1134.43
  4725.5 1133.92  4759.2 1131.96  4777.8 1132.90  4783.2 1131.19  4807.2 1133.08
  4836.6 1130.09  4853.8 1131.35  4884.5 1129.67  4907.9 1126.76  4919.3 1123.48
  4967.2 1118.88  5019.3 1117.78  5082.9 1123.20  5104.2 1121.43  5111.2 1122.68
  5146.6 1121.16  5153.7 1122.58  5194.0 1117.69  5194.2 1117.19  5198.2 1117.69
  5210.2 1123.69  5231.5 1126.32  5505.3 1133.38  5536.4 1134.69  5698.1 1141.17
#Mann=9,-1,0
  4453.8    0.05       0  4509.7    0.12       0  4634.4    0.05       0
  4652.4    0.12       0  4725.5    0.05       0  5194.0    0.03       0
  5198.2    0.05       0  5505.3    0.12       0  5536.4    0.05       0
Bank Sta=5194,5198.2
Exp/Cntr=0.3,0.1

Type RM Length L Ch R = 1,9000,477,477,477
BEGIN DESCRIPTION:
SANFERNANDO059 18.0
END DESCRIPTION:
XS GIS Cut Line= 3
      2796855.69     10264003.07      2796936.58     10263364.67
      2796755.68     10262853.11
#Sta/Elev= 30
  4356.5 1137.38  4357.4 1137.38  4376.6 1137.90  4437.1 1135.80  4467.3 1135.93
  4474.1 1134.63  4648.8 1127.72  4709.3 1126.25  4749.6 1123.96  4840.3 1123.43
  4860.8 1122.33  4880.6 1120.99  4941.1 1119.56  4949.6 1117.30  4954.7 1117.48
  4959.3 1116.25  4996.0 1114.36  4996.3 1113.86  5000.6 1114.36  5012.3 1114.67
  5017.6 1117.43  5022.9 1116.95  5043.2 1120.13  5074.1 1123.18  5166.9 1125.49
  5203.2 1125.47  5217.4 1126.62  5273.7 1128.22  5383.5 1131.47  5542.6 1137.57
#Mann=8,-1,0
  4356.5    0.05       0  4357.4    0.12       0  4860.8    0.05       0
  4959.3    0.12       0  4996.0    0.07       0  5000.6    0.12       0
  5217.4    0.05       0  5273.7    0.12       0
Bank Sta=4996,5000.6
Exp/Cntr=0.3,0.1

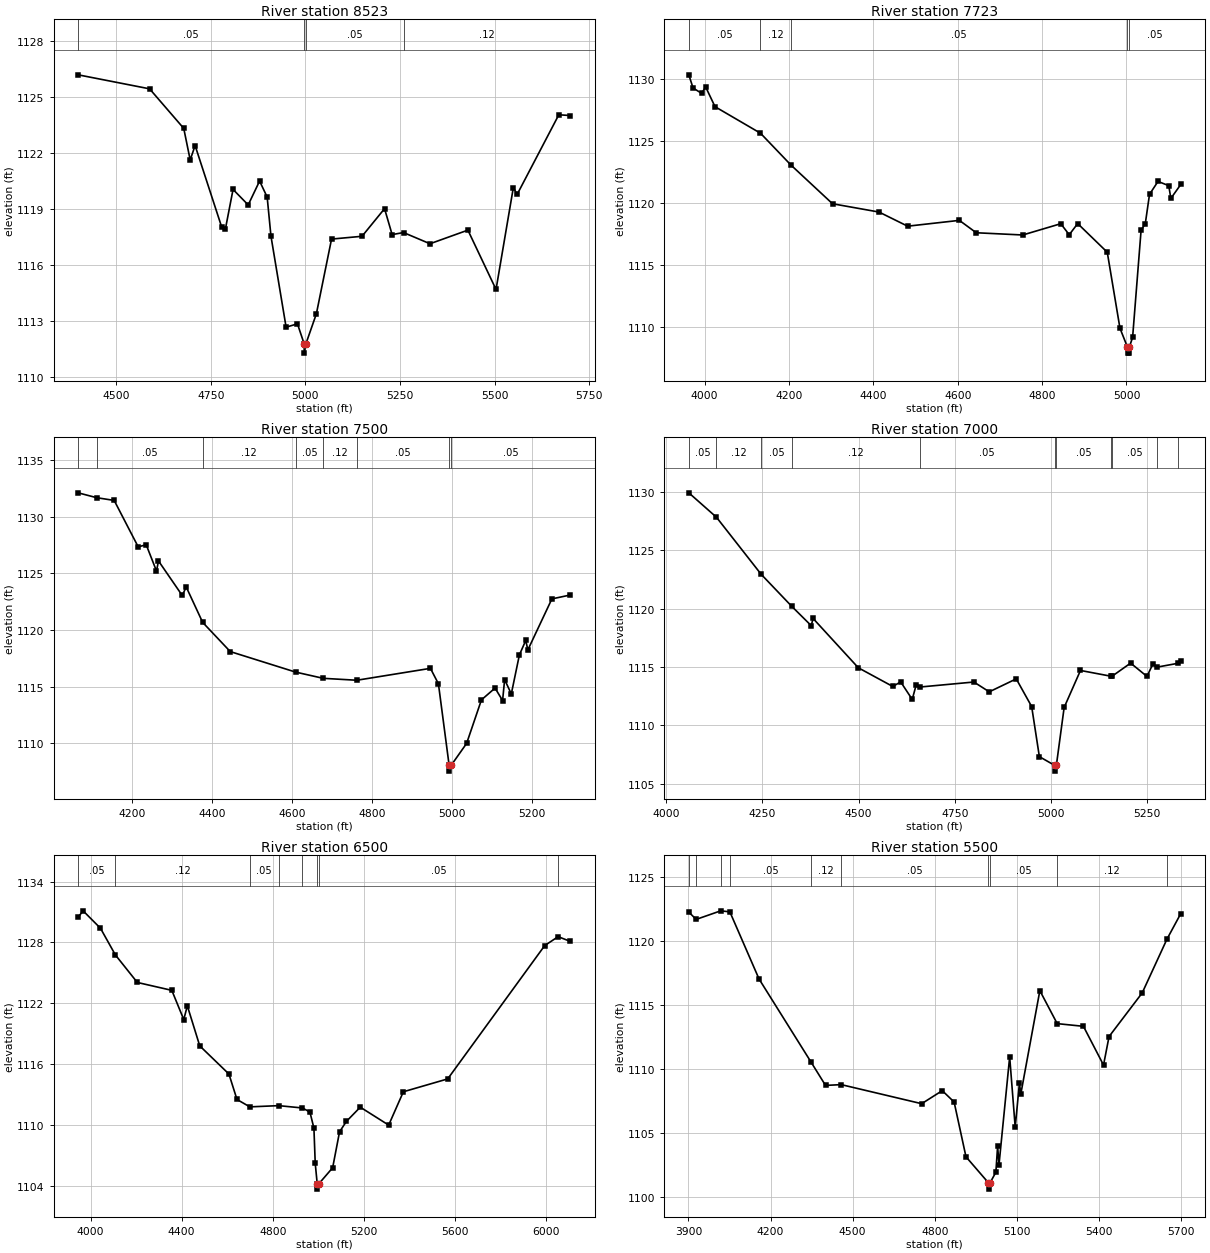
Type RM Length L Ch R = 1,8523,800,800,800
BEGIN DESCRIPTION:
Mapping XS 5b04d8c5
END DESCRIPTION:
XS GIS Cut Line= 4
      2797374.16     10263961.57      2797399.37     10263507.77
      2797399.37     10263264.05      2797416.18     10262663.20
#Sta/Elev= 30
  4399.8 1126.20  4588.5 1125.45  4678.7 1123.33  4695.7 1121.64  4708.7 1122.41
  4778.8 1118.05  4788.9 1117.96  4808.9 1120.06  4848.9 1119.23  4879.0 1120.51
  4899.0 1119.65  4909.0 1117.56  4949.0 1112.68  4979.0 1112.86  4996.6 1111.79
  4997.0 1111.29  5001.3 1111.79  5029.0 1113.40  5069.0 1117.40  5149.5 1117.55
  5209.0 1119.03  5229.0 1117.64  5259.1 1117.75  5329.0 1117.15  5429.1 1117.88
  5503.4 1114.70  5549.1 1120.16  5559.1 1119.79  5669.2 1124.06  5699.1 1124.02
#Mann=4,-1,0
  4399.8    0.05       0  4996.6    0.05       0  5001.3    0.05       0
  5259.1    0.12       0
Bank Sta=4996.6,5001.3
Exp/Cntr=0.3,0.1

Type RM Length L Ch R = 1,7723,223,223,223
BEGIN DESCRIPTION:
Mapping XS b6672c4a
END DESCRIPTION:
XS GIS Cut Line= 2
      2797596.86     10263743.13      2797672.50     10262579.09
#Sta/Elev= 30
  3962.4 1130.37  3972.4 1129.31  3992.5 1128.88  4002.5 1129.38  4024.5 1127.80
  4132.3 1125.66  4204.6 1123.09  4303.1 1119.97  4413.4 1119.30  4481.2 1118.16
  4603.8 1118.63  4643.9 1117.63  4754.1 1117.45  4844.3 1118.36  4864.3 1117.47
  4884.4 1118.37  4954.5 1116.06  4984.6 1109.93  5002.2 1108.42  5002.6 1107.92
  5006.7 1107.92  5007.0 1108.42  5014.6 1109.19  5034.7 1117.83  5044.7 1118.37
  5054.7 1120.73  5074.8 1121.77  5100.3 1121.43  5105.3 1120.40  5128.9 1121.53
#Mann=5,-1,0
  3962.4    0.05       0  4132.3    0.12       0  4204.6    0.05       0
  5002.2    0.05       0  5007.0    0.05       0
Bank Sta=5002.2,5007
Exp/Cntr=0.3,0.1

Type RM Length L Ch R = 1,7500,500,500,500
BEGIN DESCRIPTION:
SANFERNANDO059 15.0
END DESCRIPTION:
XS GIS Cut Line= 3
      2797955.69     10263653.12      2797884.42     10262719.84
      2797830.69     10262428.15
#Sta/Elev= 30
  4064.0 1132.11  4110.5 1131.68  4154.3 1131.44  4214.5 1127.34  4234.5 1127.53
  4260.3 1125.21  4265.3 1126.10  4324.8 1123.05  4334.8 1123.80  4375.9 1120.68
  4445.1 1118.10  4608.8 1116.29  4677.9 1115.74  4762.2 1115.57  4946.6 1116.62
  4966.6 1115.26  4993.5 1108.05  4993.8 1107.55  4998.3 1108.05  5037.3 1110.00
  5074.4 1113.84  5108.5 1114.88  5127.4 1113.78  5132.5 1115.63  5149.2 1114.36
  5169.5 1117.81  5185.5 1119.09  5190.6 1118.24  5250.9 1122.75  5296.6 1123.09
#Mann=8,-1,0
  4064.0    0.12       0  4110.5    0.05       0  4375.9    0.12       0
  4608.8    0.05       0  4677.9    0.12       0  4762.2    0.05       0
  4993.5    0.05       0  4998.3    0.05       0
Bank Sta=4993.5,4998.3
Exp/Cntr=0.3,0.1

Type RM Length L Ch R = 1,7000,500,500,500
BEGIN DESCRIPTION:
SANFERNANDO059 14.0
END DESCRIPTION:
XS GIS Cut Line= 3
      2798405.68     10263553.09      2798361.65     10262612.92
      2798180.71     10262328.15
#Sta/Elev= 30
  4058.8 1129.91  4130.6 1127.82  4246.9 1122.93  4326.0 1120.20  4376.8 1118.54
  4381.8 1119.15  4499.3 1114.93  4588.8 1113.33  4609.4 1113.72  4639.4 1112.22
  4649.4 1113.43  4659.1 1113.28  4799.6 1113.71  4839.6 1112.87  4909.7 1113.98
  4949.8 1111.61  4969.8 1107.32  5009.2 1106.58  5009.6 1106.08  5014.0 1106.58
  5034.2 1111.53  5076.6 1114.70  5156.9 1114.20  5158.9 1114.21  5207.0 1115.33
  5249.4 1114.19  5264.6 1115.24  5276.5 1114.99  5331.3 1115.32  5337.4 1115.49
#Mann=11,-1,0
  4058.8    0.05       0  4130.6    0.12       0  4246.9    0.05       0
  4326.0    0.12       0  4659.1    0.05       0  5009.2    0.05       0
  5014.0    0.05       0  5156.9    0.12       0  5158.9    0.05       0
  5276.5    0.12       0  5331.3    0.05       0
Bank Sta=5009.2,5014
Exp/Cntr=0.3,0.1

Type RM Length L Ch R = 1,6500,1000,1000,1000
BEGIN DESCRIPTION:
SANFERNANDO059 13.0
END DESCRIPTION:
XS GIS Cut Line= 3
      2798405.68     10263603.12      2798825.74     10262635.78
      2798663.81     10261541.10
#Sta/Elev= 30
  3945.4 1130.49  3967.2 1131.12  4043.5 1129.40  4108.9 1126.77  4205.3 1124.05
  4356.9 1123.27  4409.3 1120.39  4425.1 1121.74  4479.6 1117.79  4607.8 1115.01
  4643.1 1112.50  4699.6 1111.77  4826.4 1111.89  4930.6 1111.66  4963.5 1111.26
  4981.1 1109.67  4986.9 1106.18  4995.7 1104.15  4996.2 1103.65  5001.7 1104.15
  5063.4 1105.76  5093.7 1109.31  5124.0 1110.34  5184.7 1111.74  5309.5 1109.97
  5374.0 1113.26  5568.8 1114.53  5994.9 1127.69  6053.9 1128.57  6106.6 1128.11
#Mann=8,-1,0
  3945.4    0.05       0  4108.9    0.12       0  4699.6    0.05       0
  4826.4    0.12       0  4930.6    0.05       0  4995.7    0.03       0
  5001.7    0.05       0  6053.9    0.12       0
Bank Sta=4995.7,5001.7
Exp/Cntr=0.3,0.1

Type RM Length L Ch R = 1,5500,500,500,500
BEGIN DESCRIPTION:
SANFERNANDO059 11.0
END DESCRIPTION:
XS GIS Cut Line= 3
      2798955.66     10263203.15      2799494.60     10262245.94
      2799405.69     10261553.12
#Sta/Elev= 30
  3901.5 1122.24  3928.4 1121.67  4018.0 1122.34  4051.4 1122.26  4158.0 1117.01
  4348.3 1110.50  4400.8 1108.69  4458.3 1108.75  4752.0 1107.26  4827.2 1108.28
  4870.5 1107.39  4913.8 1103.11  4995.6 1101.08  4996.1 1100.58  5001.9 1101.08
  5023.0 1101.90  5029.4 1103.94  5034.4 1102.49  5073.4 1110.92  5093.6 1105.42
  5109.0 1108.86  5114.1 1108.02  5183.6 1116.10  5247.0 1113.52  5342.8 1113.31
  5416.2 1110.28  5436.4 1112.51  5557.4 1115.92  5648.0 1120.13  5698.5 1122.13
#Mann=10,-1,0
  3901.5    0.12       0  3928.4    0.05       0  4018.0    0.12       0
  4051.4    0.05       0  4348.3    0.12       0  4458.3    0.05       0
  4995.6    0.03       0  5001.9    0.05       0  5247.0    0.12       0
  5648.0    0.05       0
Bank Sta=4995.6,5001.9
Exp/Cntr=0.3,0.1

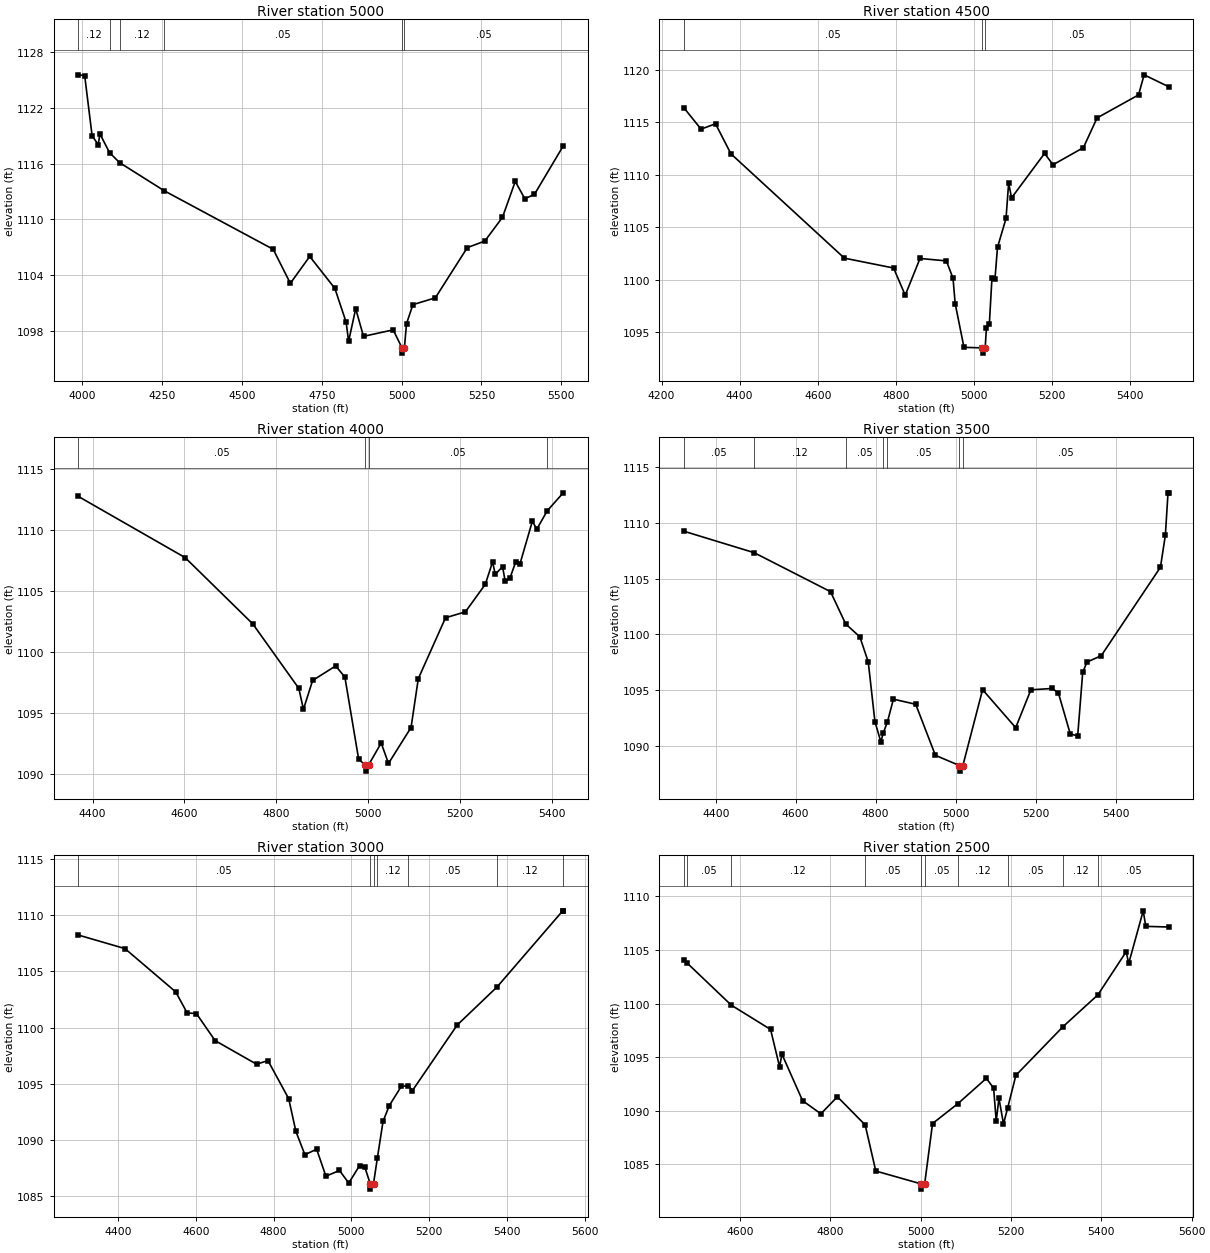
Type RM Length L Ch R = 1,5000,500,500,500
BEGIN DESCRIPTION:
SANFERNANDO059 10.0
END DESCRIPTION:
XS GIS Cut Line= 3
      2800255.70     10263403.15      2799886.58     10262458.29
      2799855.69     10261953.14
#Sta/Elev= 30
  3985.6 1125.59  4007.1 1125.51  4030.4 1119.01  4049.5 1118.07  4054.9 1119.22
  4084.9 1117.20  4116.4 1116.12  4256.5 1113.08  4597.6 1106.77  4651.3 1103.10
  4712.1 1106.00  4790.8 1102.55  4826.1 1098.90  4833.8 1096.84  4856.0 1100.36
  4880.5 1097.38  4973.4 1098.08  5002.0 1096.07  5002.5 1095.57  5008.4 1096.07
  5015.2 1098.74  5035.2 1100.80  5105.4 1101.53  5205.6 1106.95  5260.5 1107.66
  5315.8 1110.22  5355.8 1114.09  5385.9 1112.22  5416.0 1112.70  5506.1 1117.92
#Mann=6,-1,0
  3985.6    0.12       0  4084.9    0.05       0  4116.4    0.12       0
  4256.5    0.05       0  5002.0    0.03       0  5008.4    0.05       0
Bank Sta=5002,5008.4
Exp/Cntr=0.3,0.1

Type RM Length L Ch R = 1,4500,500,500,500
BEGIN DESCRIPTION:
SANFERNANDO059 9.0
END DESCRIPTION:
XS GIS Cut Line= 3
      2800605.68     10262953.11      2800279.68     10262285.00
      2799905.70     10261953.13
#Sta/Elev= 30
  4256.6 1116.41  4301.1 1114.35  4338.2 1114.86  4377.7 1112.00  4668.3 1102.07
  4794.4 1101.13  4824.1 1098.54  4862.0 1102.04  4929.5 1101.81  4946.5 1100.16
  4952.1 1097.74  4974.6 1093.58  5021.9 1093.53  5022.4 1093.03  5028.9 1093.53
  5032.1 1095.42  5039.6 1095.81  5046.3 1100.18  5053.9 1100.05  5060.5 1103.10
  5082.3 1105.85  5089.0 1109.22  5096.5 1107.81  5181.0 1112.04  5202.7 1110.96
  5280.5 1112.59  5315.6 1115.42  5421.8 1117.61  5436.0 1119.52  5500.0 1118.37
#Mann=3,-1,0
  4256.6    0.05       0  5021.9    0.05       0  5028.9    0.05       0
Bank Sta=5021.9,5028.9
Exp/Cntr=0.3,0.1

Type RM Length L Ch R = 1,4000,500,500,500
BEGIN DESCRIPTION:
SANFERNANDO059 8.0
END DESCRIPTION:
XS GIS Cut Line= 3
      2800805.68     10262803.07      2800764.75     10262172.40
      2800555.67     10261803.08
#Sta/Elev= 30
  4368.0 1112.77  4601.5 1107.74  4748.8 1102.31  4849.0 1097.03  4859.0 1095.32
  4879.0 1097.68  4929.1 1098.87  4949.2 1097.96  4979.2 1091.23  4993.6 1090.76
  4994.1 1090.26  5000.7 1090.76  5028.2 1092.56  5044.1 1090.89  5093.2 1093.83
  5109.0 1097.83  5168.2 1102.81  5211.5 1103.30  5254.8 1105.55  5270.7 1107.39
  5276.4 1106.37  5292.3 1106.99  5298.1 1105.80  5308.2 1106.03  5320.9 1107.38
  5329.9 1107.18  5357.2 1110.71  5366.9 1110.07  5389.6 1111.57  5424.4 1113.04
#Mann=4,-1,0
  4368.0    0.05       0  4993.6    0.05       0  5000.7    0.05       0
  5389.6    0.12       0
Bank Sta=4993.6,5000.7
Exp/Cntr=0.3,0.1

Type RM Length L Ch R = 1,3500,500,500,500
BEGIN DESCRIPTION:
SANFERNANDO059 7.0
END DESCRIPTION:
XS GIS Cut Line= 3
      2801405.67     10262603.07      2801199.91     10261954.84
      2800705.70     10261753.12
#Sta/Elev= 30
  4319.9 1109.26  4496.0 1107.33  4687.1 1103.83  4725.1 1100.93  4760.5 1099.77
  4781.5 1097.52  4798.2 1092.16  4813.0 1090.35  4818.7 1091.10  4829.6 1092.16
  4844.4 1094.18  4900.2 1093.72  4949.4 1089.14  5009.6 1088.22  5010.1 1087.72
  5018.1 1088.22  5067.4 1095.03  5150.2 1091.62  5188.2 1095.02  5242.2 1095.14
  5257.2 1094.71  5286.6 1091.07  5305.2 1090.87  5317.8 1096.59  5328.6 1097.51
  5364.1 1098.08  5512.2 1106.02  5524.5 1108.90  5531.1 1112.70  5533.8 1112.70
#Mann=7,-1,0
  4319.9    0.05       0  4496.0    0.12       0  4725.1    0.05       0
  4818.7    0.12       0  4829.6    0.05       0  5009.6    0.05       0
  5018.1    0.05       0
Bank Sta=5009.6,5018.1
Exp/Cntr=0.3,0.1

Type RM Length L Ch R = 1,3000,500,500,500
BEGIN DESCRIPTION:
SANFERNANDO059 6.0
END DESCRIPTION:
XS GIS Cut Line= 3
      2801405.68     10262453.12      2801673.43     10261802.78
      2801455.66     10261303.07
#Sta/Elev= 30
  4296.7 1108.24  4418.0 1107.02  4548.5 1103.17  4577.9 1101.30  4601.8 1101.24
  4649.7 1098.84  4756.4 1096.74  4785.7 1097.06  4839.0 1093.68  4857.5 1090.77
  4880.7 1088.69  4910.9 1089.18  4934.8 1086.78  4969.6 1087.29  4993.5 1086.17
  5021.5 1087.73  5034.9 1087.58  5048.5 1086.13  5049.0 1085.63  5057.2 1086.13
  5067.1 1088.40  5081.7 1091.66  5097.8 1093.06  5128.6 1094.77  5146.3 1094.82
  5157.4 1094.40  5272.3 1100.22  5375.2 1103.62  5543.8 1110.38  5545.1 1110.38
#Mann=7,-1,0
  4296.7    0.05       0  5048.5    0.03       0  5057.2    0.05       0
  5067.1    0.12       0  5146.3    0.05       0  5375.2    0.12       0
  5543.8    0.05       0
Bank Sta=5048.5,5057.2
Exp/Cntr=0.3,0.1

Type RM Length L Ch R = 1,2500,500,500,500
BEGIN DESCRIPTION:
SANFERNANDO059 5.0
END DESCRIPTION:
XS GIS Cut Line= 3
      2802055.69     10262453.09      2802140.24     10261934.84
      2802405.67     10261453.13
#Sta/Elev= 30
  4474.9 1104.02  4481.5 1103.82  4580.3 1099.85  4667.4 1097.58  4687.4 1094.08
  4692.5 1095.28  4738.3 1090.93  4778.8 1089.71  4815.4 1091.30  4876.9 1088.67
  4900.4 1084.37  4999.9 1083.18  5000.4 1082.68  5008.7 1083.18  5026.1 1088.80
  5082.6 1090.67  5145.3 1093.02  5161.4 1092.10  5167.1 1089.04  5173.2 1091.16
  5183.2 1088.77  5192.2 1090.21  5210.7 1093.30  5315.3 1097.85  5392.3 1100.81
  5454.9 1104.83  5460.6 1103.75  5492.7 1108.65  5498.4 1107.20  5550.0 1107.14
#Mann=10,-1,0
  4474.9    0.12       0  4481.5    0.05       0  4580.3    0.12       0
  4876.9    0.05       0  4999.9    0.03       0  5008.7    0.05       0
  5082.6    0.12       0  5192.2    0.05       0  5315.3    0.12       0
  5392.3    0.05       0
Bank Sta=4999.9,5008.7
Exp/Cntr=0.3,0.1