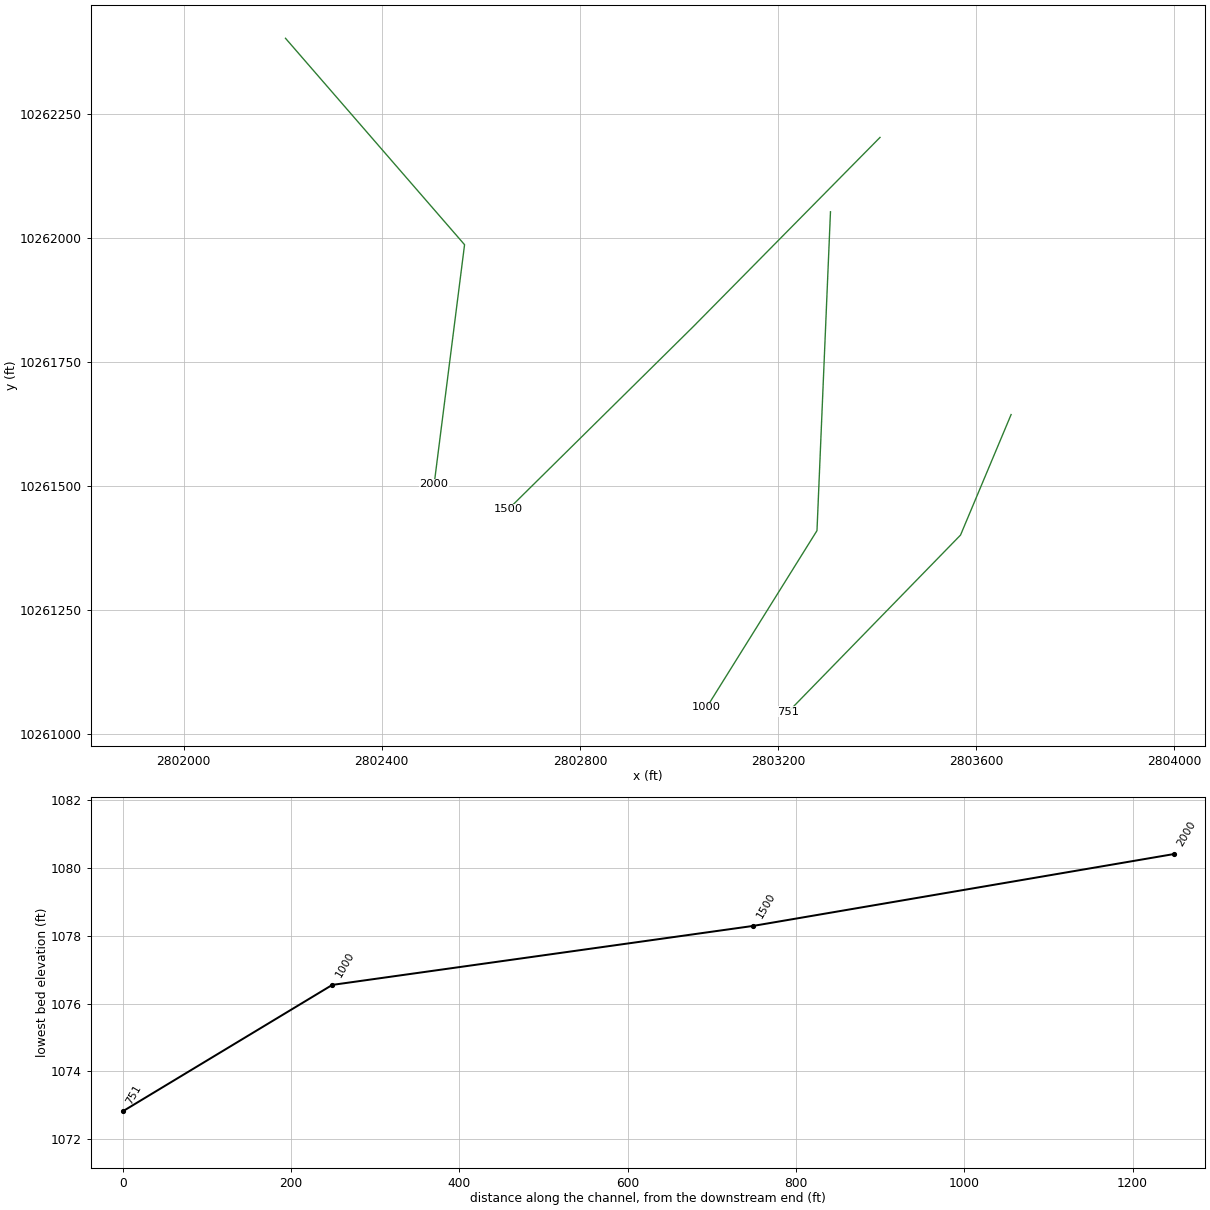
HEC-RAS study SANFERNANDO059.prj: SANFERNANDO059 Base Level Engineering

--- SANFERNANDO059.g01 (geometry) --- (continued)

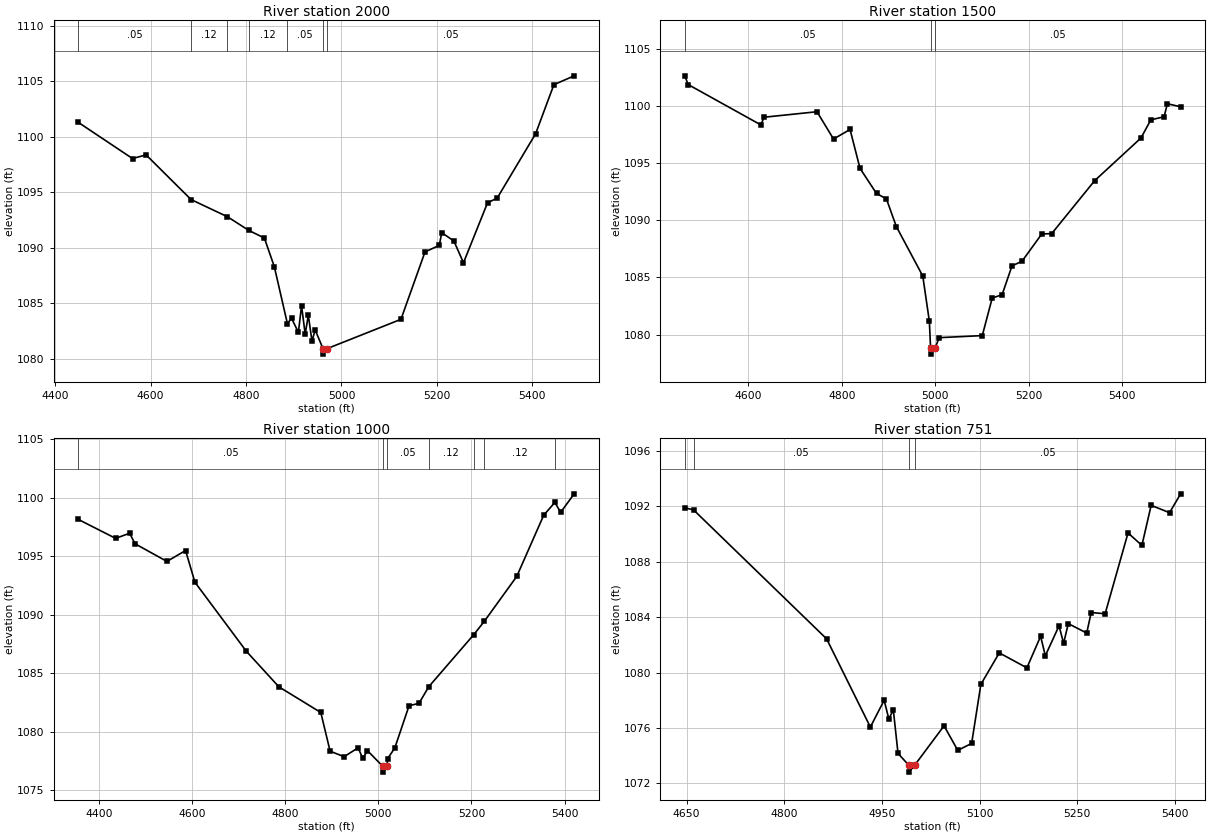
Type RM Length L Ch R = 1,2000,500,500,500
BEGIN DESCRIPTION:
SANFERNANDO059 4.0
END DESCRIPTION:
XS GIS Cut Line= 3
      2802205.68     10262403.12      2802567.13     10261986.71
      2802505.68     10261503.10
#Sta/Elev= 30
  4448.6 1101.31  4562.1 1098.05  4590.6 1098.38  4684.8 1094.35  4761.1 1092.80
  4805.7 1091.57  4838.4 1090.88  4859.3 1088.29  4886.6 1083.17  4895.4 1083.64
  4909.7 1082.37  4916.3 1084.77  4923.9 1082.22  4930.5 1083.91  4938.2 1081.58
  4944.8 1082.60  4961.2 1080.91  4961.7 1080.41  4970.1 1080.91  5124.6 1083.55
  5175.0 1089.63  5205.0 1090.22  5210.0 1091.37  5235.5 1090.61  5255.6 1088.65
  5306.0 1094.06  5326.2 1094.48  5406.8 1100.29  5445.0 1104.71  5487.5 1105.51
#Mann=7,-1,0
  4448.6    0.05       0  4684.8    0.12       0  4761.1    0.05       0
  4805.7    0.12       0  4886.6    0.05       0  4961.2    0.05       0
  4970.1    0.05       0
Bank Sta=4961.2,4970.1
Exp/Cntr=0.3,0.1

Type RM Length L Ch R = 1,1500,500,500,500
BEGIN DESCRIPTION:
SANFERNANDO059 3.0
END DESCRIPTION:
XS GIS Cut Line= 3
      2803405.67     10262203.10      2803029.18     10261821.87
      2802655.66     10261453.09
#Sta/Elev= 30
  4464.2 1102.63  4471.3 1101.87  4626.8 1098.34  4633.9 1099.01  4747.0 1099.49
  4782.4 1097.10  4817.7 1097.94  4839.0 1094.54  4874.3 1092.34  4895.5 1091.87
  4916.7 1089.45  4973.3 1085.12  4987.4 1081.16  4990.0 1078.79  4990.5 1078.29
  4999.0 1078.79  5008.6 1079.73  5100.6 1079.91  5121.8 1083.19  5143.0 1083.49
  5164.2 1086.01  5185.5 1086.41  5227.9 1088.80  5249.1 1088.83  5341.0 1093.46
  5440.0 1097.19  5461.2 1098.78  5489.5 1099.05  5496.6 1100.19  5524.9 1099.92
#Mann=3,-1,0
  4464.2    0.05       0  4990.0    0.03       0  4999.0    0.05       0
Bank Sta=4990,4999
Exp/Cntr=0.3,0.1

Type RM Length L Ch R = 1,1000,249,249,249
BEGIN DESCRIPTION:
SANFERNANDO059 2.0
END DESCRIPTION:
XS GIS Cut Line= 3
      2803305.69     10262053.14      2803278.46     10261409.92
      2803055.70     10261053.14
#Sta/Elev= 30
  4356.2 1098.16  4436.3 1096.54  4466.3 1096.98  4477.9 1096.08  4546.4 1094.57
  4586.4 1095.50  4606.5 1092.79  4716.6 1086.90  4786.6 1083.85  4876.7 1081.65
  4896.7 1078.34  4926.7 1077.87  4956.8 1078.63  4966.8 1077.72  4976.8 1078.39
  5009.7 1077.05  5010.2 1076.55  5018.8 1077.05  5020.2 1077.71  5035.5 1078.61
  5066.2 1082.23  5087.4 1082.43  5108.6 1083.86  5204.7 1088.29  5227.6 1089.44
  5297.4 1093.29  5355.2 1098.52  5379.1 1099.61  5391.7 1098.77  5420.6 1100.35
#Mann=7,-1,0
  4356.2    0.05       0  5009.7    0.05       0  5018.8    0.05       0
  5108.6    0.12       0  5204.7    0.05       0  5227.6    0.12       0
  5379.1    0.05       0
Bank Sta=5009.7,5018.8
Exp/Cntr=0.3,0.1

Type RM Length L Ch R = 1,751,0,0,0
BEGIN DESCRIPTION:
SANFERNANDO059 1.0
END DESCRIPTION:
XS GIS Cut Line= 3
      2803670.26     10261644.02      2803568.18     10261400.92
      2803220.46     10261044.22
#Sta/Elev= 30
  4647.1 1091.88  4660.6 1091.73  4865.0 1082.43  4932.2 1076.07  4953.4 1078.00
  4960.5 1076.67  4967.5 1077.30  4974.7 1074.17  4991.2 1073.32  4991.7 1072.82
  5000.3 1073.32  5045.4 1076.16  5066.5 1074.39  5087.8 1074.89  5102.0 1079.15
  5130.3 1081.42  5172.7 1080.34  5193.8 1082.62  5201.0 1081.21  5222.1 1083.37
  5229.1 1082.11  5236.3 1083.53  5264.6 1082.85  5271.5 1084.33  5292.9 1084.24
  5328.1 1090.07  5349.4 1089.17  5363.6 1092.06  5391.9 1091.53  5408.9 1092.89
#Mann=4,-1,0
  4647.1    0.12       0  4660.6    0.05       0  4991.2    0.05       0
  5000.3    0.05       0
Bank Sta=4991.2,5000.3
Exp/Cntr=0.3,0.1

Chan Stop Cuts=-1