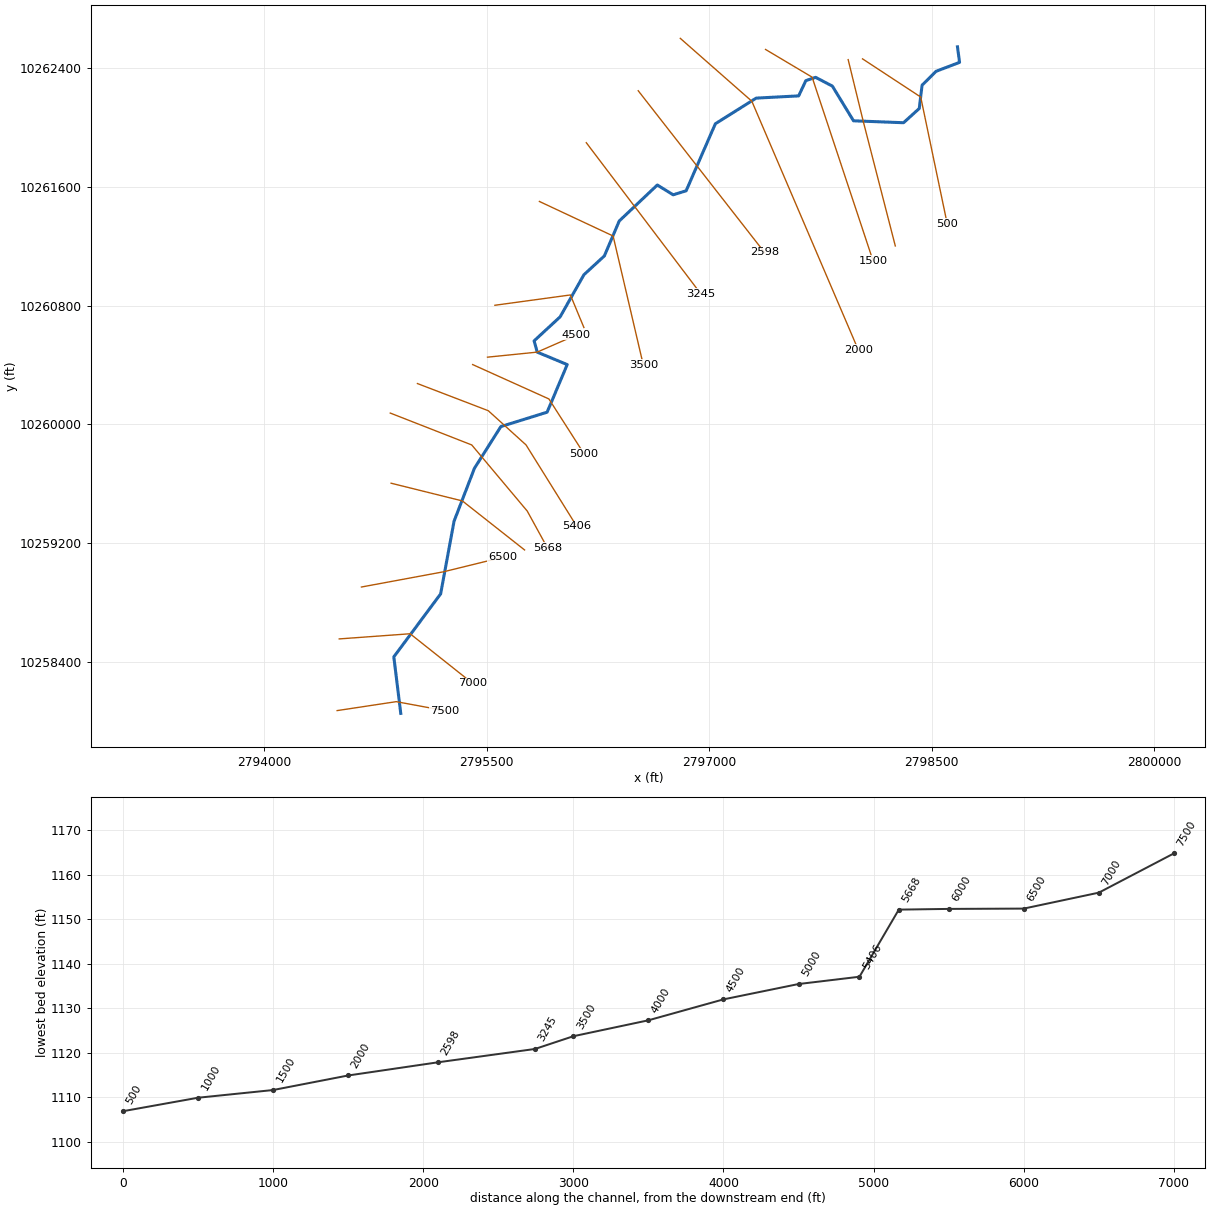
--- SANFERNANDO060.prj (project) ---

Proj Title=SANFERNANDO060 Base Level Engineering
Current Plan=p01
Default Exp/Contr=0.3,0.1
English Units
Geom File=g01
Flow File=f01
Plan File=p01
BEGIN DESCRIPTION:
SANFERNANDO060
END DESCRIPTION:

--- SANFERNANDO060.p01 (plan) ---

Plan Title=Multiple Run
Short Identifier=Multiple
Geom File=g01
Flow File=f01
Subcritical Flow
K Sum by GR= 0
Std Step Tol= 0.01
Critical Tol= 0.01
Num of Std Step Trials= 20
Max Error Tol= 0.3
Flow Tol Ratio= 0.001
Split Flow NTrial= 30
Split Flow Tol= 0.02
Split Flow Ratio= 0.02
Log Output Level= 0
Friction Slope Method= 1
Unsteady Friction Slope Method= 2
Unsteady Bridges Friction Slope Method= 1
Parabolic Critical Depth
Global Vel Dist=  1 , 1 , 1
Global Log Level= 0
CheckData=True
Encroach Param= -1, 0, 0, 0
BEGIN DESCRIPTION:
Multiple Run
END DESCRIPTION:

--- SANFERNANDO060.f01 (steady flow) ---

Flow Title=Multiple
Number of Profiles=7
Profile Names=10-year,25-year,50-year,1pct_min,100-year,1pct_plu,500-year
River Rch & RM= SANFERNANDO060,Reach-1,7500
     303     480     525     310     677    1479     914
Boundary for River Rch & Prof#=SANFERNANDO060,Reach-1,1
Up Type=0
Dn Type=3
Dn Slope=0.005
Boundary for River Rch & Prof#=SANFERNANDO060,Reach-1,2
Up Type=0
Dn Type=3
Dn Slope=0.005
Boundary for River Rch & Prof#=SANFERNANDO060,Reach-1,3
Up Type=0
Dn Type=3
Dn Slope=0.005
Boundary for River Rch & Prof#=SANFERNANDO060,Reach-1,4
Up Type=0
Dn Type=3
Dn Slope=0.005
Boundary for River Rch & Prof#=SANFERNANDO060,Reach-1,5
Up Type=0
Dn Type=3
Dn Slope=0.005
Boundary for River Rch & Prof#=SANFERNANDO060,Reach-1,6
Up Type=0
Dn Type=3
Dn Slope=0.005
Boundary for River Rch & Prof#=SANFERNANDO060,Reach-1,7
Up Type=0
Dn Type=3
Dn Slope=0.005

--- SANFERNANDO060.g01 (geometry) ---

Geom Title=Existing Conditions

River Reach=SANFERNANDO060,Reach-1
Reach XY= 30
      2794920.75     10258051.00      2794874.00     10258432.00
      2795189.75     10258857.00      2795280.25     10259347.00
      2795417.75     10259704.00      2795595.75     10259985.00
      2795907.75     10260082.00      2796043.25     10260403.00
      2795841.00     10260487.00      2795820.00     10260563.00
      2795995.50     10260725.00      2796156.00     10261009.00
      2796294.00     10261136.00      2796393.75     10261371.00
      2796650.75     10261614.00      2796757.50     10261548.00
      2796845.25     10261575.00      2797042.25     10262027.00
      2797317.50     10262200.00      2797604.00     10262215.00
      2797652.50     10262318.00      2797718.50     10262340.00
      2797831.25     10262281.00      2797973.75     10262047.00
      2798311.25     10262034.00      2798417.25     10262130.00
      2798436.25     10262287.00      2798531.00     10262381.00
      2798689.00     10262441.00      2798675.00     10262546.00

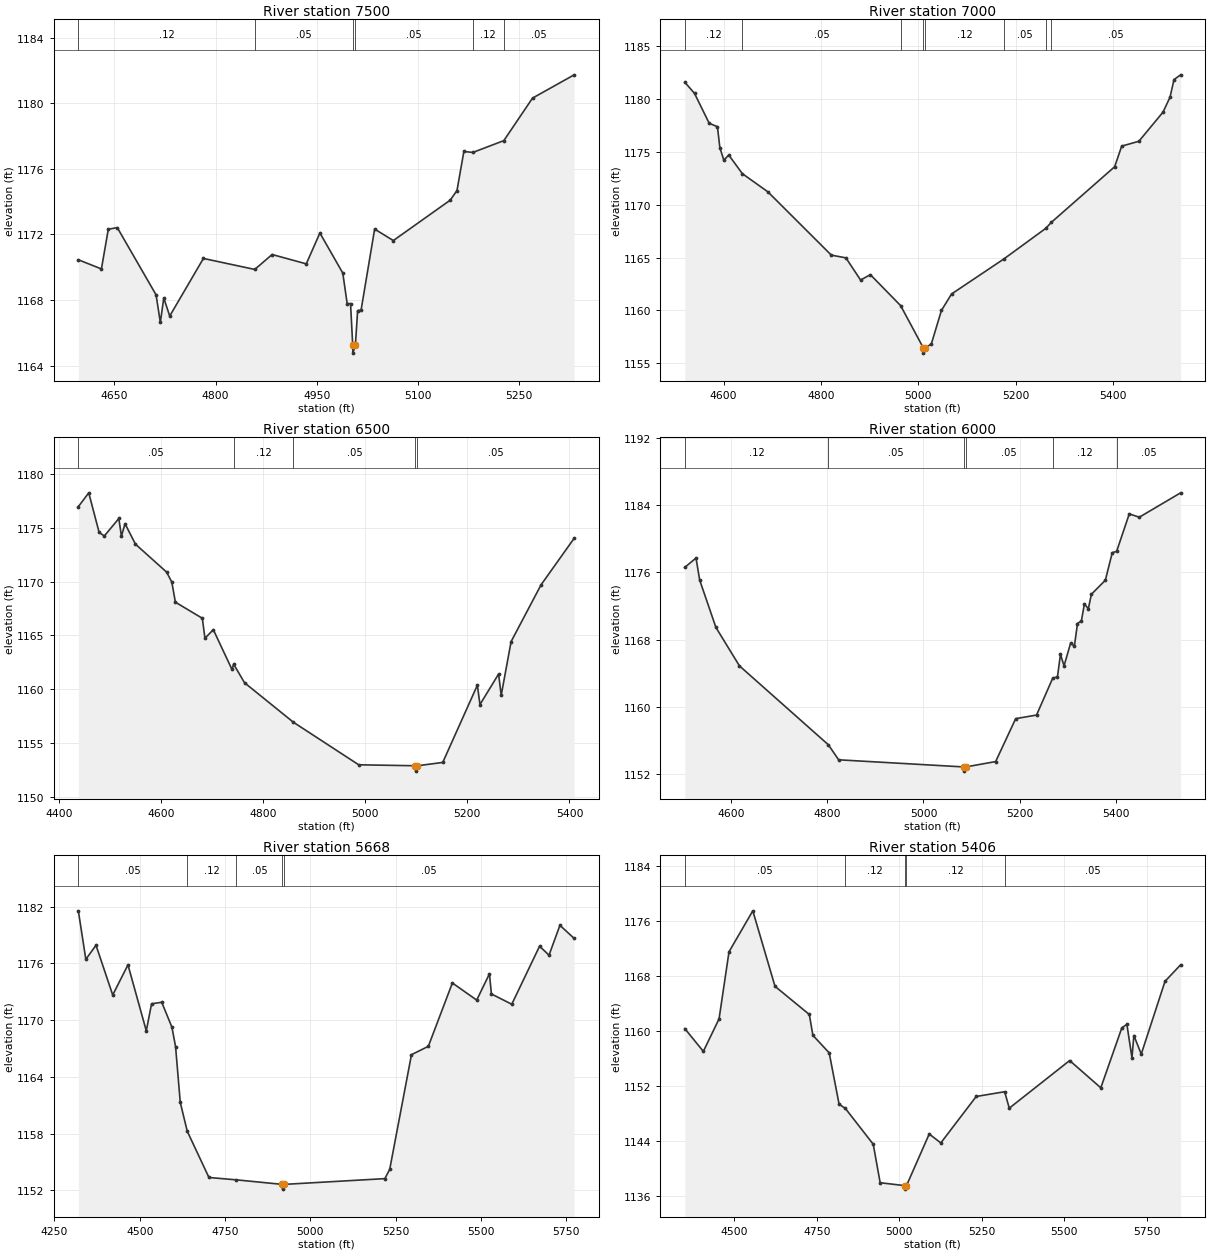
Type RM Length L Ch R = 1,7500,500,500,500
BEGIN DESCRIPTION:
SANFERNANDO060 15.0
END DESCRIPTION:
XS GIS Cut Line= 3
      2794491.82     10258069.75      2794890.59     10258130.06
      2795216.36     10258069.75
#Sta/Elev= 30
  4596.7 1170.46  4630.9 1169.90  4641.1 1172.32  4654.4 1172.42  4711.9 1168.32
  4718.2 1166.64  4723.3 1168.13  4732.1 1167.03  4782.0 1170.54  4858.1 1169.87
  4883.8 1170.78  4934.4 1170.21  4954.6 1172.09  4988.5 1169.65  4995.0 1167.79
  5000.0 1167.79  5003.2 1165.27  5003.4 1164.77  5007.2 1165.27  5010.5 1167.36
  5015.6 1167.39  5035.7 1172.33  5063.4 1171.63  5147.6 1174.09  5157.7 1174.68
  5167.9 1177.06  5181.2 1177.00  5227.1 1177.72  5269.6 1180.31  5331.3 1181.73
#Mann=6,-1,0
  4596.7    0.12       0  4858.1    0.05       0  5003.2    0.05       0
  5007.2    0.05       0  5181.2    0.12       0  5227.1    0.05       0
Bank Sta=5003.2,5007.2
Exp/Cntr=0.3,0.1

Type RM Length L Ch R = 1,7000,500,500,500
BEGIN DESCRIPTION:
SANFERNANDO060 14.0
END DESCRIPTION:
XS GIS Cut Line= 3
      2794505.71     10258553.11      2794984.05     10258587.89
      2795405.70     10258253.10
#Sta/Elev= 30
  4520.4 1181.60  4540.4 1180.54  4570.5 1177.71  4587.4 1177.39  4592.4 1175.40
  4600.6 1174.21  4610.6 1174.71  4638.6 1172.94  4690.8 1171.23  4821.2 1165.23
  4851.2 1164.97  4881.3 1162.87  4901.4 1163.38  4963.5 1160.45  5010.1 1156.45
  5010.3 1155.95  5014.1 1156.45  5026.5 1156.81  5047.3 1159.99  5068.1 1161.55
  5175.6 1164.87  5261.7 1167.77  5272.7 1168.32  5403.0 1173.60  5417.4 1175.55
  5452.7 1176.01  5502.3 1178.77  5516.7 1180.19  5524.8 1181.85  5538.4 1182.30
#Mann=8,-1,0
  4520.4    0.12       0  4638.6    0.05       0  4963.5    0.12       0
  5010.1    0.07       0  5014.1    0.12       0  5175.6    0.05       0
  5261.7    0.12       0  5272.7    0.05       0
Bank Sta=5010.1,5014.1
Exp/Cntr=0.3,0.1

Type RM Length L Ch R = 1,6500,500,500,500
BEGIN DESCRIPTION:
SANFERNANDO060 13.0
END DESCRIPTION:
XS GIS Cut Line= 3
      2794655.67     10258903.11      2795208.25     10259005.57
      2795605.66     10259103.10
#Sta/Elev= 30
  4438.0 1176.99  4458.4 1178.28  4478.7 1174.60  4488.9 1174.26  4517.3 1175.89
  4522.4 1174.25  4529.5 1175.40  4549.9 1173.50  4610.9 1170.90  4621.1 1169.97
  4628.1 1168.10  4680.9 1166.60  4686.0 1164.74  4702.4 1165.54  4738.9 1161.84
  4742.2 1162.33  4763.5 1160.60  4859.3 1156.92  4987.2 1152.96  5098.3 1152.87
  5098.6 1152.37  5102.3 1152.87  5151.8 1153.18  5219.6 1160.37  5224.7 1158.57
  5261.2 1161.41  5266.3 1159.43  5285.7 1164.43  5344.3 1169.71  5409.2 1174.05
#Mann=5,-1,0
  4438.0    0.05       0  4742.2    0.12       0  4859.3    0.05       0
  5098.3    0.03       0  5102.3    0.05       0
Bank Sta=5098.3,5102.3
Exp/Cntr=0.3,0.1

Type RM Length L Ch R = 1,6000,332,332,332
BEGIN DESCRIPTION:
SANFERNANDO060 12.0
END DESCRIPTION:
XS GIS Cut Line= 3
      2794855.67     10259603.12      2795336.54     10259483.61
      2795755.71     10259153.09
#Sta/Elev= 30
  4504.5 1176.61  4527.8 1177.72  4535.4 1175.09  4569.1 1169.44  4617.9 1164.86
  4802.4 1155.45  4823.9 1153.65  5083.7 1152.80  5083.9 1152.30  5087.7 1152.80
  5149.8 1153.44  5191.4 1158.56  5234.7 1158.99  5268.2 1163.38  5278.1 1163.56
  5284.4 1166.23  5291.8 1164.86  5305.3 1167.54  5313.3 1167.23  5319.7 1169.91
  5327.8 1170.22  5334.1 1172.25  5342.2 1171.67  5348.6 1173.40  5377.5 1175.07
  5391.9 1178.36  5401.0 1178.52  5427.2 1182.99  5448.0 1182.59  5533.8 1185.50
#Mann=6,-1,0
  4504.5    0.12       0  4802.4    0.05       0  5083.7    0.03       0
  5087.7    0.05       0  5268.2    0.12       0  5401.0    0.05       0
Bank Sta=5083.7,5087.7
Exp/Cntr=0.3,0.1

Type RM Length L Ch R = 1,5668,262,262,262
BEGIN DESCRIPTION:
Mapping XS dad6c5c1
END DESCRIPTION:
XS GIS Cut Line= 4
      2794850.14     10260076.11      2795399.48     10259861.15
      2795773.68     10259415.29      2795909.05     10259168.45
#Sta/Elev= 30
  4319.9 1181.57  4341.9 1176.44  4371.7 1177.93  4420.7 1172.67  4465.4 1175.86
  4519.1 1168.88  4534.6 1171.74  4564.4 1171.90  4594.3 1169.26  4605.0 1167.20
  4618.7 1161.31  4639.2 1158.26  4702.8 1153.37  4783.5 1153.12  4918.3 1152.64
  4918.5 1152.14  4922.3 1152.64  5218.4 1153.25  5232.7 1154.23  5296.5 1166.36
  5345.9 1167.24  5416.4 1173.94  5487.7 1172.13  5525.1 1174.91  5530.8 1172.78
  5590.5 1171.69  5672.0 1177.83  5699.7 1176.88  5731.7 1180.04  5773.4 1178.65
#Mann=5,-1,0
  4319.9    0.05       0  4639.2    0.12       0  4783.5    0.05       0
  4918.3    0.03       0  4922.3    0.05       0
Bank Sta=4918.3,4922.3
Exp/Cntr=0.3,0.1

Type RM Length L Ch R = 1,5406,406,406,406
BEGIN DESCRIPTION:
Mapping XS d809ec50
END DESCRIPTION:
XS GIS Cut Line= 4
      2795033.24     10260275.17      2795510.95     10260092.05
      2795765.72     10259861.15      2796108.06     10259311.83
#Sta/Elev= 30
  4349.5 1160.38  4405.7 1157.07  4453.4 1161.80  4483.5 1171.54  4555.6 1177.49
  4622.9 1166.52  4726.9 1162.43  4737.7 1159.40  4787.1 1156.86  4817.1 1149.40
  4836.2 1148.78  4920.6 1143.58  4941.6 1137.99  5017.3 1137.56  5017.5 1137.06
  5021.3 1137.56  5090.3 1145.07  5125.4 1143.77  5232.7 1150.52  5318.9 1151.21
  5332.9 1148.82  5515.9 1155.74  5610.3 1151.78  5674.0 1160.49  5689.3 1161.00
  5704.7 1156.16  5710.5 1159.37  5732.9 1156.68  5804.9 1167.25  5852.2 1169.65
#Mann=5,-1,0
  4349.5    0.05       0  4836.2    0.12       0  5017.3    0.07       0
  5021.3    0.12       0  5318.9    0.05       0
Bank Sta=5017.3,5021.3
Exp/Cntr=0.3,0.1

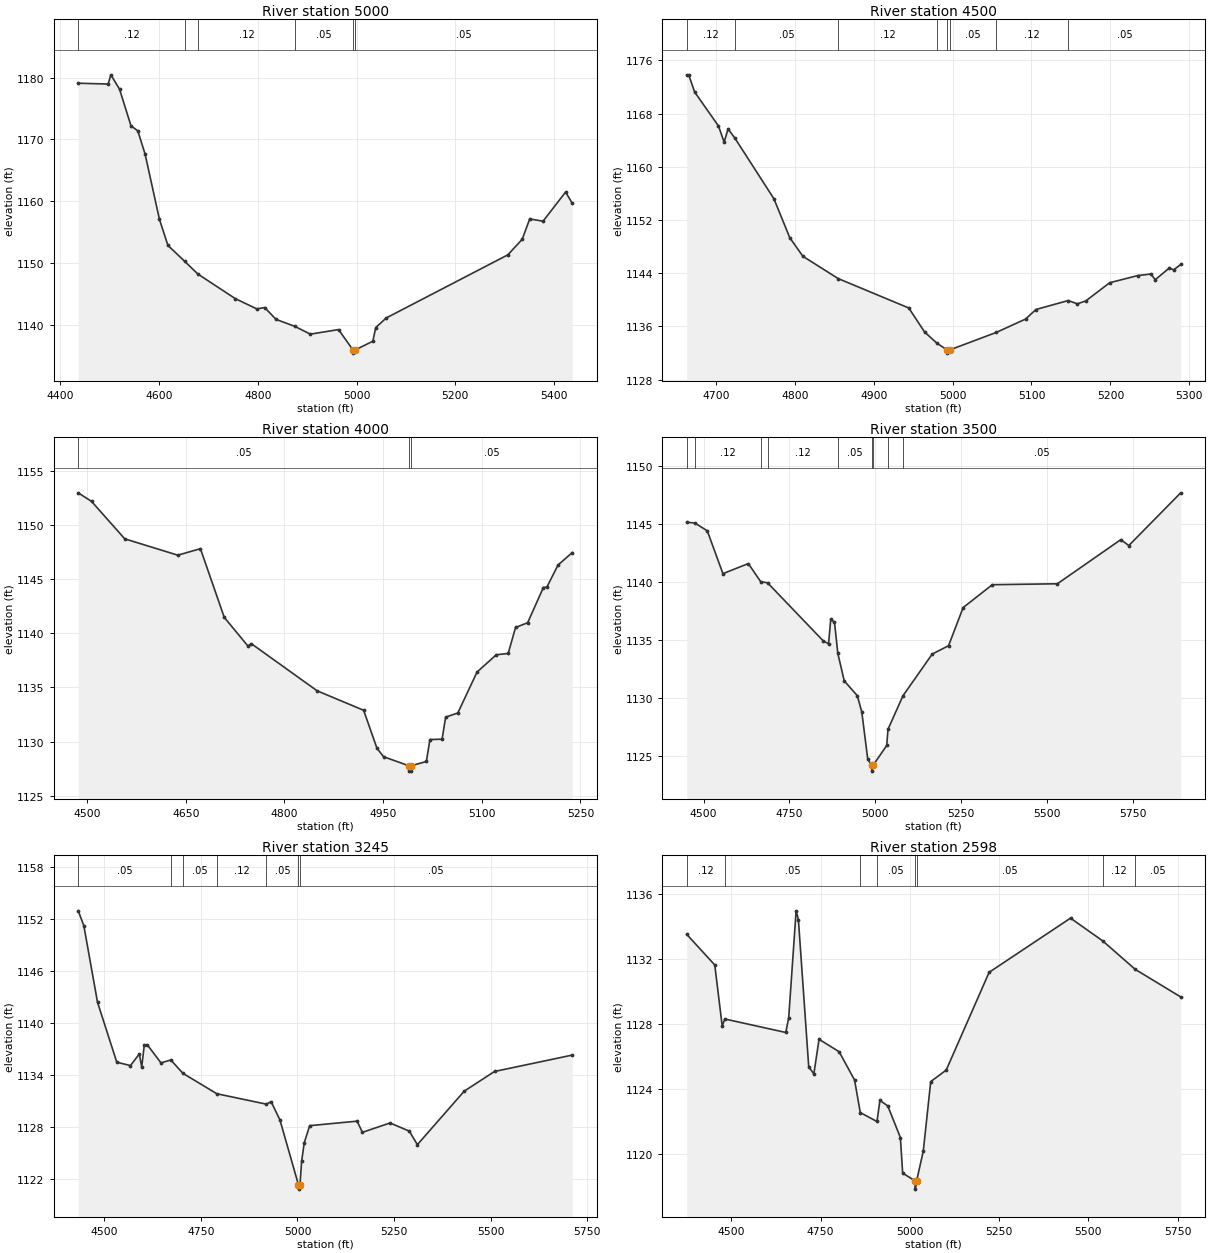
Type RM Length L Ch R = 1,5000,500,500,500
BEGIN DESCRIPTION:
SANFERNANDO060 10.0
END DESCRIPTION:
XS GIS Cut Line= 3
      2795405.67     10260403.12      2795919.82     10260171.28
      2796155.66     10259803.15
#Sta/Elev= 30
  4436.0 1179.09  4496.6 1178.96  4502.1 1180.45  4519.7 1178.13  4542.9 1172.20
  4556.7 1171.39  4571.5 1167.62  4600.6 1157.06  4617.7 1152.86  4651.5 1150.29
  4678.6 1148.21  4754.1 1144.25  4798.0 1142.57  4813.8 1142.80  4836.9 1140.88
  4875.3 1139.74  4906.3 1138.49  4963.5 1139.23  4993.0 1135.92  4993.2 1135.42
  4997.0 1135.92  5033.1 1137.35  5039.0 1139.56  5060.2 1141.11  5306.6 1151.32
  5335.8 1153.83  5351.0 1157.13  5378.1 1156.77  5423.7 1161.48  5437.2 1159.68
#Mann=6,-1,0
  4436.0    0.12       0  4651.5    0.05       0  4678.6    0.12       0
  4875.3    0.05       0  4993.0    0.05       0  4997.0    0.05       0
Bank Sta=4993,4997
Exp/Cntr=0.3,0.1

Type RM Length L Ch R = 1,4500,500,500,500
BEGIN DESCRIPTION:
SANFERNANDO060 9.0
END DESCRIPTION:
XS GIS Cut Line= 3
      2795505.71     10260453.11      2795840.89     10260487.10
      2796105.69     10260603.11
#Sta/Elev= 30
  4663.1 1173.83  4665.6 1173.83  4673.1 1171.25  4703.3 1166.14  4710.5 1163.71
  4715.5 1165.68  4723.9 1164.35  4773.6 1155.19  4793.7 1149.33  4810.3 1146.54
  4854.9 1143.19  4944.5 1138.76  4964.6 1135.14  4980.0 1133.48  4992.8 1132.47
  4993.0 1131.97  4996.8 1132.47  5055.3 1135.08  5092.6 1137.10  5105.6 1138.53
  5146.6 1139.88  5158.1 1139.38  5169.0 1139.84  5199.1 1142.56  5234.5 1143.63
  5251.3 1143.87  5256.8 1143.01  5274.7 1144.78  5280.1 1144.49  5289.1 1145.31
#Mann=8,-1,0
  4663.1    0.12       0  4723.9    0.05       0  4854.9    0.12       0
  4980.0    0.05       0  4992.8    0.05       0  4996.8    0.05       0
  5055.3    0.12       0  5146.6    0.05       0
Bank Sta=4992.8,4996.8
Exp/Cntr=0.3,0.1

Type RM Length L Ch R = 1,4000,500,500,500
BEGIN DESCRIPTION:
SANFERNANDO060 8.0
END DESCRIPTION:
XS GIS Cut Line= 3
      2795555.68     10260803.11      2796064.56     10260872.58
      2796155.67     10260653.14
#Sta/Elev= 30
  4486.4 1152.98  4506.6 1152.19  4557.1 1148.73  4637.8 1147.22  4672.2 1147.82
  4708.4 1141.48  4744.5 1138.82  4749.5 1139.05  4849.7 1134.69  4920.4 1132.89
  4940.6 1129.39  4950.7 1128.60  4989.0 1127.77  4989.3 1127.27  4992.8 1127.27
  4993.0 1127.77  5015.8 1128.16  5021.2 1130.19  5039.7 1130.22  5045.1 1132.26
  5063.6 1132.64  5092.8 1136.42  5122.1 1138.02  5140.2 1138.14  5151.4 1140.54
  5169.8 1140.98  5193.7 1144.23  5199.1 1144.28  5216.0 1146.31  5237.6 1147.46
#Mann=3,-1,0
  4486.4    0.05       0  4989.0    0.05       0  4993.0    0.05       0
Bank Sta=4989,4993
Exp/Cntr=0.3,0.1

Type RM Length L Ch R = 1,3500,255,255,255
BEGIN DESCRIPTION:
SANFERNANDO060 7.0
END DESCRIPTION:
XS GIS Cut Line= 3
      2795855.66     10261503.12      2796352.80     10261270.20
      2796555.68     10260403.12
#Sta/Elev= 30
  4451.0 1145.12  4474.7 1145.05  4510.9 1144.38  4556.5 1140.69  4630.5 1141.56
  4666.6 1140.00  4686.7 1139.90  4848.6 1134.91  4864.3 1134.65  4870.7 1136.75
  4881.6 1136.51  4891.3 1133.83  4910.0 1131.46  4948.0 1130.19  4961.2 1128.78
  4978.5 1124.72  4990.1 1124.19  4990.4 1123.69  4994.1 1124.19  5033.8 1125.90
  5037.5 1127.29  5081.2 1130.18  5166.4 1133.77  5214.0 1134.49  5256.5 1137.77
  5341.5 1139.74  5531.1 1139.82  5715.9 1143.62  5739.2 1143.11  5890.5 1147.65
#Mann=9,-1,0
  4451.0    0.05       0  4474.7    0.12       0  4666.6    0.05       0
  4686.7    0.12       0  4891.3    0.05       0  4990.1    0.05       0
  4994.1    0.05       0  5037.5    0.12       0  5081.2    0.05       0
Bank Sta=4990.1,4994.1
Exp/Cntr=0.3,0.1

Type RM Length L Ch R = 1,3245,647,647,647
BEGIN DESCRIPTION:
Mapping XS a521da99
END DESCRIPTION:
XS GIS Cut Line= 2
      2796171.75     10261899.40      2796944.06     10260880.28
#Sta/Elev= 30
  4432.6 1152.93  4447.1 1151.21  4482.5 1142.38  4532.4 1135.47  4567.8 1135.08
  4590.6 1136.41  4596.9 1134.92  4603.6 1137.45  4611.4 1137.48  4646.8 1135.39
  4672.2 1135.73  4703.7 1134.18  4791.5 1131.83  4919.7 1130.63  4931.8 1130.92
  4954.7 1128.81  5002.6 1121.33  5002.8 1120.83  5006.6 1121.33  5010.9 1124.06
  5017.7 1126.19  5031.7 1128.15  5154.4 1128.67  5168.2 1127.38  5239.7 1128.46
  5289.6 1127.52  5310.4 1125.96  5431.7 1132.13  5510.1 1134.40  5711.3 1136.29
#Mann=7,-1,0
  4432.6    0.05       0  4672.2    0.12       0  4703.7    0.05       0
  4791.5    0.12       0  4919.7    0.05       0  5002.6    0.05       0
  5006.6    0.05       0
Bank Sta=5002.6,5006.6
Exp/Cntr=0.3,0.1

Type RM Length L Ch R = 1,2598,598,598,598
BEGIN DESCRIPTION:
Mapping XS ea95aec0
END DESCRIPTION:
XS GIS Cut Line= 2
      2796522.08     10262249.71      2797373.97     10261158.96
#Sta/Elev= 30
  4375.0 1133.54  4453.6 1131.65  4474.4 1127.89  4481.8 1128.32  4652.5 1127.49
  4660.7 1128.39  4681.5 1134.99  4687.9 1134.44  4716.8 1125.38  4731.2 1124.93
  4745.7 1127.07  4802.1 1126.30  4845.2 1124.56  4861.3 1122.55  4908.0 1122.00
  4916.3 1123.30  4938.3 1122.96  4973.6 1121.01  4980.0 1118.82  5015.0 1118.33
  5015.3 1117.83  5019.0 1118.33  5037.8 1120.18  5058.6 1124.46  5102.0 1125.17
  5222.3 1131.20  5450.3 1134.54  5540.8 1133.13  5631.6 1131.38  5759.0 1129.68
#Mann=8,-1,0
  4375.0    0.12       0  4481.8    0.05       0  4861.3    0.12       0
  4908.0    0.05       0  5015.0    0.05       0  5019.0    0.05       0
  5540.8    0.12       0  5631.6    0.05       0
Bank Sta=5015,5019
Exp/Cntr=0.3,0.1

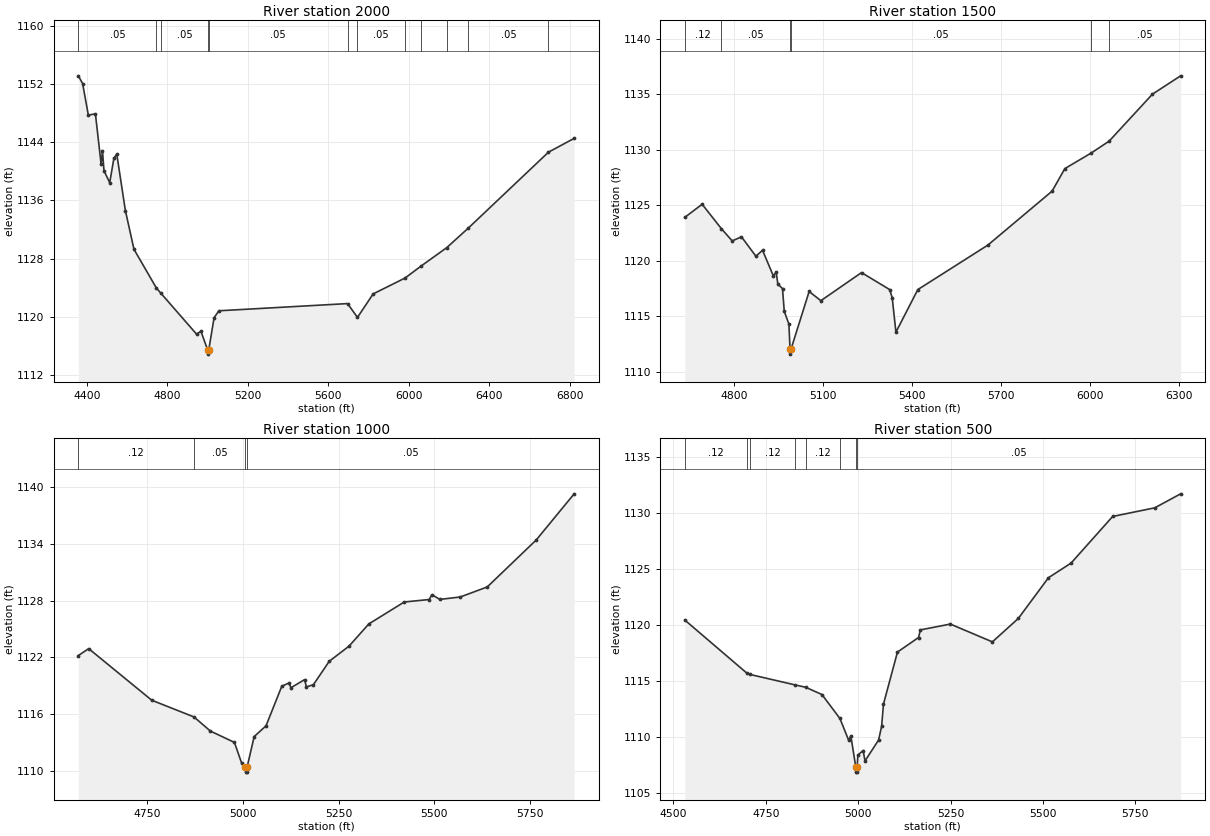
Type RM Length L Ch R = 1,2000,500,500,500
BEGIN DESCRIPTION:
SANFERNANDO060 4.0
END DESCRIPTION:
XS GIS Cut Line= 3
      2796805.70     10262603.10      2797288.35     10262178.86
      2798005.67     10260503.14
#Sta/Elev= 30
  4357.4 1153.14  4378.7 1152.08  4407.2 1147.73  4442.3 1147.92  4470.8 1140.97
  4477.4 1142.85  4485.0 1140.08  4513.5 1138.45  4534.3 1141.82  4548.6 1142.36
  4591.3 1134.62  4634.0 1129.29  4745.1 1123.98  4767.7 1123.25  4945.2 1117.62
  4967.0 1118.01  5001.4 1115.37  5001.6 1114.87  5005.4 1115.37  5032.4 1119.87
  5056.0 1120.83  5696.1 1121.82  5745.4 1119.92  5823.3 1123.15  5982.4 1125.34
  6062.2 1126.99  6189.6 1129.52  6297.2 1132.22  6694.9 1142.64  6822.8 1144.54
#Mann=12,-1,0
  4357.4    0.05       0  4745.1    0.12       0  4767.7    0.05       0
  5001.4    0.05       0  5005.4    0.05       0  5696.1    0.12       0
  5745.4    0.05       0  5982.4    0.12       0  6062.2    0.05       0
  6189.6    0.12       0  6297.2    0.05       0  6694.9    0.12       0
Bank Sta=5001.4,5005.4
Exp/Cntr=0.3,0.1

Type RM Length L Ch R = 1,1500,500,500,500
BEGIN DESCRIPTION:
SANFERNANDO060 3.0
END DESCRIPTION:
XS GIS Cut Line= 3
      2797380.68     10262528.12      2797694.60     10262341.32
      2798105.70     10261103.07
#Sta/Elev= 30
  4634.7 1123.91  4693.1 1125.09  4758.3 1122.88  4794.4 1121.79  4825.6 1122.16
  4874.2 1120.41  4896.5 1120.95  4932.6 1118.66  4942.4 1118.97  4948.2 1117.90
  4963.8 1117.50  4969.7 1115.45  4985.3 1114.31  4989.1 1112.10  4989.3 1111.60
  4993.1 1112.10  5053.5 1117.24  5092.9 1116.41  5229.9 1118.94  5324.7 1117.41
  5333.3 1116.68  5345.8 1113.58  5419.6 1117.41  5655.3 1121.41  5871.8 1126.27
  5914.8 1128.30  6004.0 1129.71  6063.9 1130.77  6209.8 1135.00  6304.7 1136.65
#Mann=6,-1,0
  4634.7    0.12       0  4758.3    0.05       0  4989.1    0.03       0
  4993.1    0.05       0  6004.0    0.12       0  6063.9    0.05       0
Bank Sta=4989.1,4993.1
Exp/Cntr=0.3,0.1

Type RM Length L Ch R = 1,1000,500,500,500
BEGIN DESCRIPTION:
SANFERNANDO060 2.0
END DESCRIPTION:
XS GIS Cut Line= 3
      2797937.83     10262459.45      2798040.06     10262041.06
      2798255.67     10261203.16
#Sta/Elev= 30
  4569.3 1122.19  4596.4 1122.92  4761.1 1117.47  4871.6 1115.70  4914.4 1114.21
  4977.3 1113.01  4996.4 1110.79  5006.2 1110.37  5006.5 1109.87  5010.0 1109.87
  5010.2 1110.37  5028.9 1113.63  5059.8 1114.76  5101.1 1118.95  5119.8 1119.29
  5124.9 1118.79  5160.5 1119.64  5165.6 1118.88  5183.7 1119.11  5225.0 1121.58
  5276.7 1123.18  5328.5 1125.53  5421.2 1127.85  5486.2 1128.11  5493.5 1128.62
  5514.2 1128.12  5567.6 1128.38  5638.1 1129.44  5766.0 1134.40  5865.2 1139.28
#Mann=4,-1,0
  4569.3    0.12       0  4871.6    0.05       0  5006.2    0.03       0
  5010.2    0.05       0
Bank Sta=5006.2,5010.2
Exp/Cntr=0.3,0.1

Type RM Length L Ch R = 1,500,0,0,0
BEGIN DESCRIPTION:
SANFERNANDO060 1.0
END DESCRIPTION:
XS GIS Cut Line= 3
      2798034.85     10262464.65      2798427.10     10262207.20
      2798605.69     10261353.07
#Sta/Elev= 30
  4530.8 1120.42  4698.7 1115.68  4707.4 1115.56  4829.0 1114.63  4857.6 1114.42
  4901.9 1113.77  4950.6 1111.63  4974.3 1109.68  4980.2 1110.07  4993.3 1107.34
  4993.6 1106.84  4997.1 1106.84  4997.3 1107.34  4999.2 1108.36  5013.4 1108.77
  5018.5 1107.84  5055.3 1109.71  5063.4 1110.93  5068.5 1112.92  5106.3 1117.56
  5163.3 1118.86  5168.4 1119.54  5249.4 1120.06  5363.2 1118.47  5433.3 1120.56
  5515.0 1124.20  5576.3 1125.51  5688.7 1129.67  5802.7 1130.44  5872.6 1131.69
#Mann=8,-1,0
  4530.8    0.12       0  4698.7    0.05       0  4707.4    0.12       0
  4829.0    0.05       0  4857.6    0.12       0  4950.6    0.05       0
  4993.3    0.05       0  4997.3    0.05       0
Bank Sta=4993.3,4997.3
Exp/Cntr=0.3,0.1

Chan Stop Cuts=-1