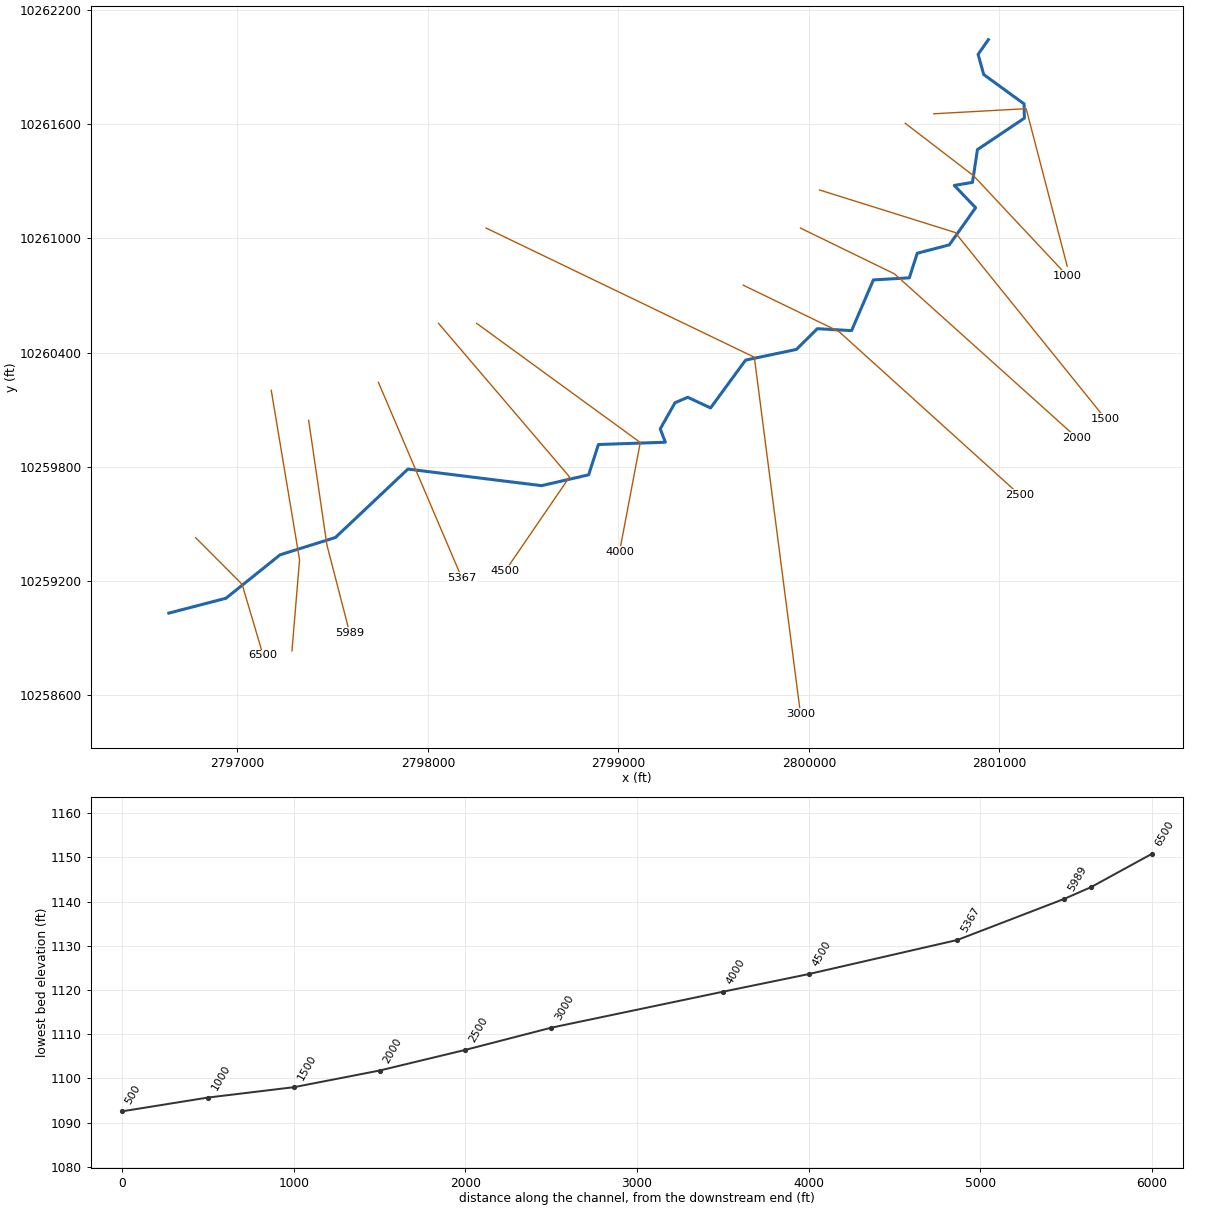
--- SANFERNANDO061.prj (project) ---

Proj Title=SANFERNANDO061 Base Level Engineering
Current Plan=p01
Default Exp/Contr=0.3,0.1
English Units
Geom File=g01
Flow File=f01
Plan File=p01
BEGIN DESCRIPTION:
SANFERNANDO061
END DESCRIPTION:

--- SANFERNANDO061.p01 (plan) ---

Plan Title=Multiple Run
Short Identifier=Multiple
Geom File=g01
Flow File=f01
Subcritical Flow
K Sum by GR= 0
Std Step Tol= 0.01
Critical Tol= 0.01
Num of Std Step Trials= 20
Max Error Tol= 0.3
Flow Tol Ratio= 0.001
Split Flow NTrial= 30
Split Flow Tol= 0.02
Split Flow Ratio= 0.02
Log Output Level= 0
Friction Slope Method= 1
Unsteady Friction Slope Method= 2
Unsteady Bridges Friction Slope Method= 1
Parabolic Critical Depth
Global Vel Dist=  1 , 1 , 1
Global Log Level= 0
CheckData=True
Encroach Param= -1, 0, 0, 0
BEGIN DESCRIPTION:
Multiple Run
END DESCRIPTION:

--- SANFERNANDO061.f01 (steady flow) ---

Flow Title=Multiple
Number of Profiles=7
Profile Names=10-year,25-year,50-year,1pct_min,100-year,1pct_plu,500-year
River Rch & RM= SANFERNANDO061,Reach-1,6500
     277     436     537     340     699    1439     958
Boundary for River Rch & Prof#=SANFERNANDO061,Reach-1,1
Up Type=0
Dn Type=3
Dn Slope=0.005
Boundary for River Rch & Prof#=SANFERNANDO061,Reach-1,2
Up Type=0
Dn Type=3
Dn Slope=0.005
Boundary for River Rch & Prof#=SANFERNANDO061,Reach-1,3
Up Type=0
Dn Type=3
Dn Slope=0.005
Boundary for River Rch & Prof#=SANFERNANDO061,Reach-1,4
Up Type=0
Dn Type=3
Dn Slope=0.005
Boundary for River Rch & Prof#=SANFERNANDO061,Reach-1,5
Up Type=0
Dn Type=3
Dn Slope=0.005
Boundary for River Rch & Prof#=SANFERNANDO061,Reach-1,6
Up Type=0
Dn Type=3
Dn Slope=0.005
Boundary for River Rch & Prof#=SANFERNANDO061,Reach-1,7
Up Type=0
Dn Type=3
Dn Slope=0.005

--- SANFERNANDO061.g01 (geometry) ---

Geom Title=Existing Conditions

River Reach=SANFERNANDO061,Reach-1
Reach XY= 30
      2796640.00     10259032.00      2796939.75     10259110.00
      2797224.00     10259338.00      2797514.50     10259429.00
      2797895.00     10259788.00      2798596.50     10259701.00
      2798843.75     10259758.00      2798895.00     10259917.00
      2799246.50     10259929.00      2799219.50     10259999.00
      2799296.75     10260136.00      2799364.00     10260165.00
      2799483.75     10260109.00      2799667.50     10260360.00
      2799934.00     10260416.00      2800044.25     10260525.00
      2800224.00     10260515.00      2800338.25     10260781.00
      2800527.00     10260792.00      2800568.50     10260921.00
      2800737.00     10260965.00      2800875.00     10261160.00
      2800763.00     10261277.00      2800858.50     10261293.00
      2800884.50     10261465.00      2801131.00     10261630.00
      2801129.25     10261705.00      2800917.50     10261859.00
      2800888.00     10261965.00      2800941.75     10262042.00

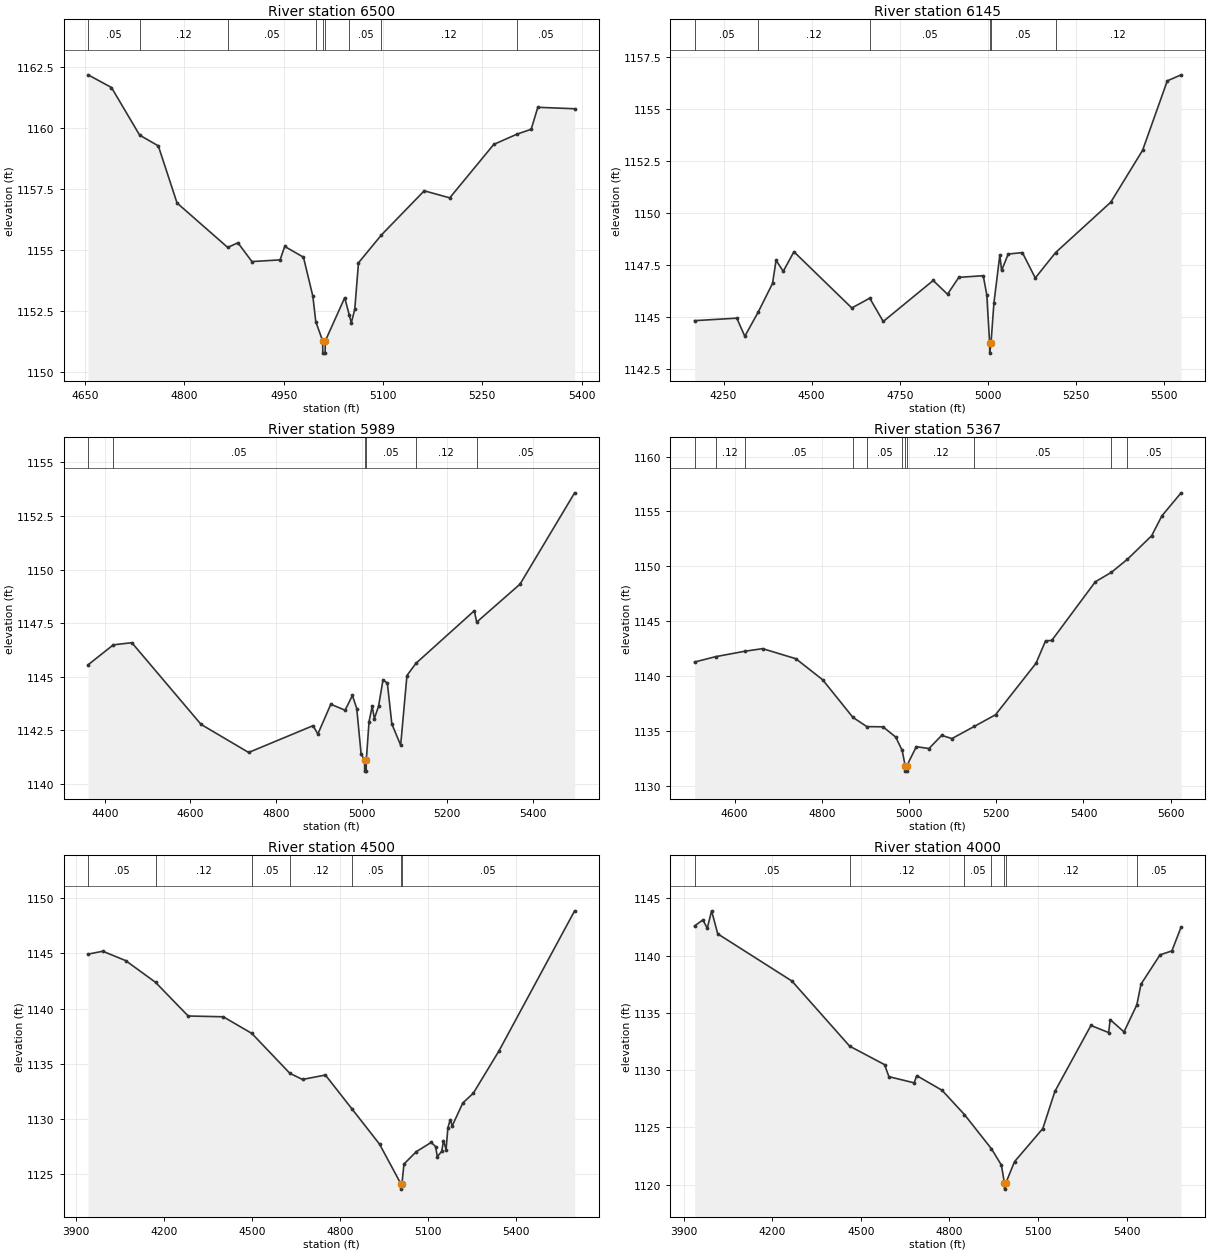
Type RM Length L Ch R = 1,6500,355,355,355
BEGIN DESCRIPTION:
SANFERNANDO061 12.0
END DESCRIPTION:
XS GIS Cut Line= 3
      2796780.71     10259428.08      2797024.52     10259183.56
      2797135.15     10258810.21
#Sta/Elev= 30
  4654.7 1162.19  4690.0 1161.67  4732.5 1159.72  4760.7 1159.28  4789.0 1156.94
  4865.5 1155.12  4880.9 1155.31  4902.1 1154.54  4944.6 1154.61  4951.6 1155.16
  4979.9 1154.72  4994.1 1153.12  4998.5 1152.08  5008.9 1151.29  5009.1 1150.79
  5012.6 1150.79  5012.9 1151.29  5042.2 1153.06  5049.1 1152.35  5052.2 1152.03
  5057.4 1152.59  5063.0 1154.49  5097.6 1155.63  5162.3 1157.44  5200.8 1157.15
  5267.3 1159.34  5302.4 1159.76  5323.8 1159.96  5333.8 1160.86  5389.4 1160.80
#Mann=9,-1,0
  4654.7    0.05       0  4732.5    0.12       0  4865.5    0.05       0
  4998.5    0.12       0  5008.9    0.07       0  5012.9    0.12       0
  5049.1    0.05       0  5097.6    0.12       0  5302.4    0.05       0
Bank Sta=5008.9,5012.9
Exp/Cntr=0.3,0.1

Type RM Length L Ch R = 1,6145,156,156,156
BEGIN DESCRIPTION:
Mapping XS 3fd19529
END DESCRIPTION:
XS GIS Cut Line= 3
      2797177.64     10260201.38      2797326.23     10259311.79
      2797286.42     10258834.06
#Sta/Elev= 30
  4167.6 1144.81  4287.5 1144.93  4310.2 1144.06  4348.8 1145.24  4388.9 1146.60
  4399.0 1147.71  4419.3 1147.18  4449.7 1148.12  4614.0 1145.42  4664.9 1145.89
  4703.2 1144.77  4845.1 1146.74  4885.7 1146.08  4917.8 1146.89  4987.1 1146.97
  4997.2 1146.06  5005.3 1143.75  5005.6 1143.25  5009.3 1143.75  5017.5 1145.66
  5034.3 1147.97  5039.3 1147.22  5058.0 1148.01  5098.3 1148.08  5134.9 1146.86
  5192.5 1148.08  5349.2 1150.50  5439.5 1152.99  5509.7 1156.33  5548.9 1156.62
#Mann=6,-1,0
  4167.6    0.05       0  4348.8    0.12       0  4664.9    0.05       0
  5005.3    0.05       0  5009.3    0.05       0  5192.5    0.12       0
Bank Sta=5005.3,5009.3
Exp/Cntr=0.3,0.1

Type RM Length L Ch R = 1,5989,622,622,622
BEGIN DESCRIPTION:
Mapping XS 49a8b930
END DESCRIPTION:
XS GIS Cut Line= 3
      2797374.01     10260044.24      2797469.54     10259391.41
      2797588.98     10258929.58
#Sta/Elev= 30
  4361.0 1145.56  4419.9 1146.49  4463.2 1146.59  4624.9 1142.78  4736.1 1141.47
  4886.6 1142.72  4897.8 1142.33  4928.1 1143.72  4961.5 1143.44  4978.6 1144.13
  4988.7 1143.52  4998.8 1141.42  5007.0 1141.10  5007.2 1140.60  5010.7 1140.60
  5011.0 1141.10  5017.4 1142.91  5024.8 1143.62  5029.9 1143.05  5039.7 1143.63
  5050.0 1144.85  5060.2 1144.71  5070.7 1142.80  5091.3 1141.81  5106.0 1145.06
  5127.1 1145.63  5263.4 1148.08  5269.0 1147.55  5370.2 1149.32  5497.8 1153.58
#Mann=6,-1,0
  4361.0    0.12       0  4419.9    0.05       0  5007.0    0.05       0
  5011.0    0.05       0  5127.1    0.12       0  5269.0    0.05       0
Bank Sta=5007,5011
Exp/Cntr=0.3,0.1

Type RM Length L Ch R = 1,5367,867,867,867
BEGIN DESCRIPTION:
Mapping XS 31800f3d
END DESCRIPTION:
XS GIS Cut Line= 2
      2797740.25     10260243.31      2798177.75     10259217.18
#Sta/Elev= 30
  4508.3 1141.27  4556.8 1141.76  4623.0 1142.25  4664.3 1142.49  4740.6 1141.57
  4802.0 1139.65  4871.4 1136.22  4903.3 1135.38  4940.4 1135.36  4969.4 1134.43
  4984.3 1133.21  4991.1 1131.82  4991.3 1131.32  4994.8 1131.32  4995.1 1131.82
  5016.7 1133.55  5045.7 1133.38  5074.8 1134.58  5098.4 1134.29  5149.7 1135.40
  5198.3 1136.46  5291.2 1141.16  5313.0 1143.20  5327.3 1143.24  5427.2 1148.59
  5464.0 1149.45  5500.7 1150.64  5556.2 1152.78  5579.8 1154.60  5623.8 1156.70
#Mann=11,-1,0
  4508.3    0.05       0  4556.8    0.12       0  4623.0    0.05       0
  4871.4    0.12       0  4903.3    0.05       0  4984.3    0.12       0
  4991.1    0.07       0  4995.1    0.12       0  5149.7    0.05       0
  5464.0    0.12       0  5500.7    0.05       0
Bank Sta=4991.1,4995.1
Exp/Cntr=0.3,0.1

Type RM Length L Ch R = 1,4500,500,500,500
BEGIN DESCRIPTION:
SANFERNANDO061 8.0
END DESCRIPTION:
XS GIS Cut Line= 3
      2798055.66     10260553.14      2798743.52     10259747.03
      2798405.69     10259253.11
#Sta/Elev= 30
  3940.3 1144.94  3990.3 1145.20  4068.3 1144.35  4170.0 1142.38  4281.3 1139.32
  4400.9 1139.25  4498.2 1137.74  4628.1 1134.11  4671.0 1133.56  4749.0 1133.96
  4838.8 1130.91  4933.4 1127.69  5005.9 1124.10  5006.2 1123.60  5009.9 1124.10
  5016.8 1125.88  5058.7 1127.00  5109.5 1127.84  5124.4 1127.47  5130.5 1126.55
  5145.4 1127.03  5151.5 1128.01  5160.3 1127.19  5166.4 1129.16  5174.4 1129.90
  5181.3 1129.35  5217.2 1131.42  5253.1 1132.31  5339.7 1136.11  5598.4 1148.87
#Mann=7,-1,0
  3940.3    0.05       0  4170.0    0.12       0  4498.2    0.05       0
  4628.1    0.12       0  4838.8    0.05       0  5005.9    0.05       0
  5009.9    0.05       0
Bank Sta=5005.9,5009.9
Exp/Cntr=0.3,0.1

Type RM Length L Ch R = 1,4000,1000,1000,1000
BEGIN DESCRIPTION:
SANFERNANDO061 7.0
END DESCRIPTION:
XS GIS Cut Line= 3
      2798255.67     10260553.12      2799114.72     10259927.70
      2799005.69     10259353.16
#Sta/Elev= 30
  3937.4 1142.59  3965.6 1143.12  3980.3 1142.39  3995.0 1143.91  4015.8 1141.90
  4267.0 1137.78  4462.7 1132.09  4580.7 1130.48  4595.4 1129.43  4681.1 1128.89
  4689.6 1129.52  4775.4 1128.24  4851.2 1126.12  4942.7 1123.13  4976.3 1121.71
  4986.8 1120.11  4987.1 1119.61  4990.8 1120.11  5020.8 1122.01  5116.6 1124.90
  5157.4 1128.14  5279.5 1133.90  5339.5 1133.28  5344.6 1134.41  5391.5 1133.34
  5434.9 1135.70  5449.1 1137.51  5513.6 1140.07  5553.6 1140.41  5584.8 1142.49
#Mann=7,-1,0
  3937.4    0.05       0  4462.7    0.12       0  4851.2    0.05       0
  4942.7    0.12       0  4986.8    0.07       0  4990.8    0.12       0
  5434.9    0.05       0
Bank Sta=4986.8,4990.8
Exp/Cntr=0.3,0.1

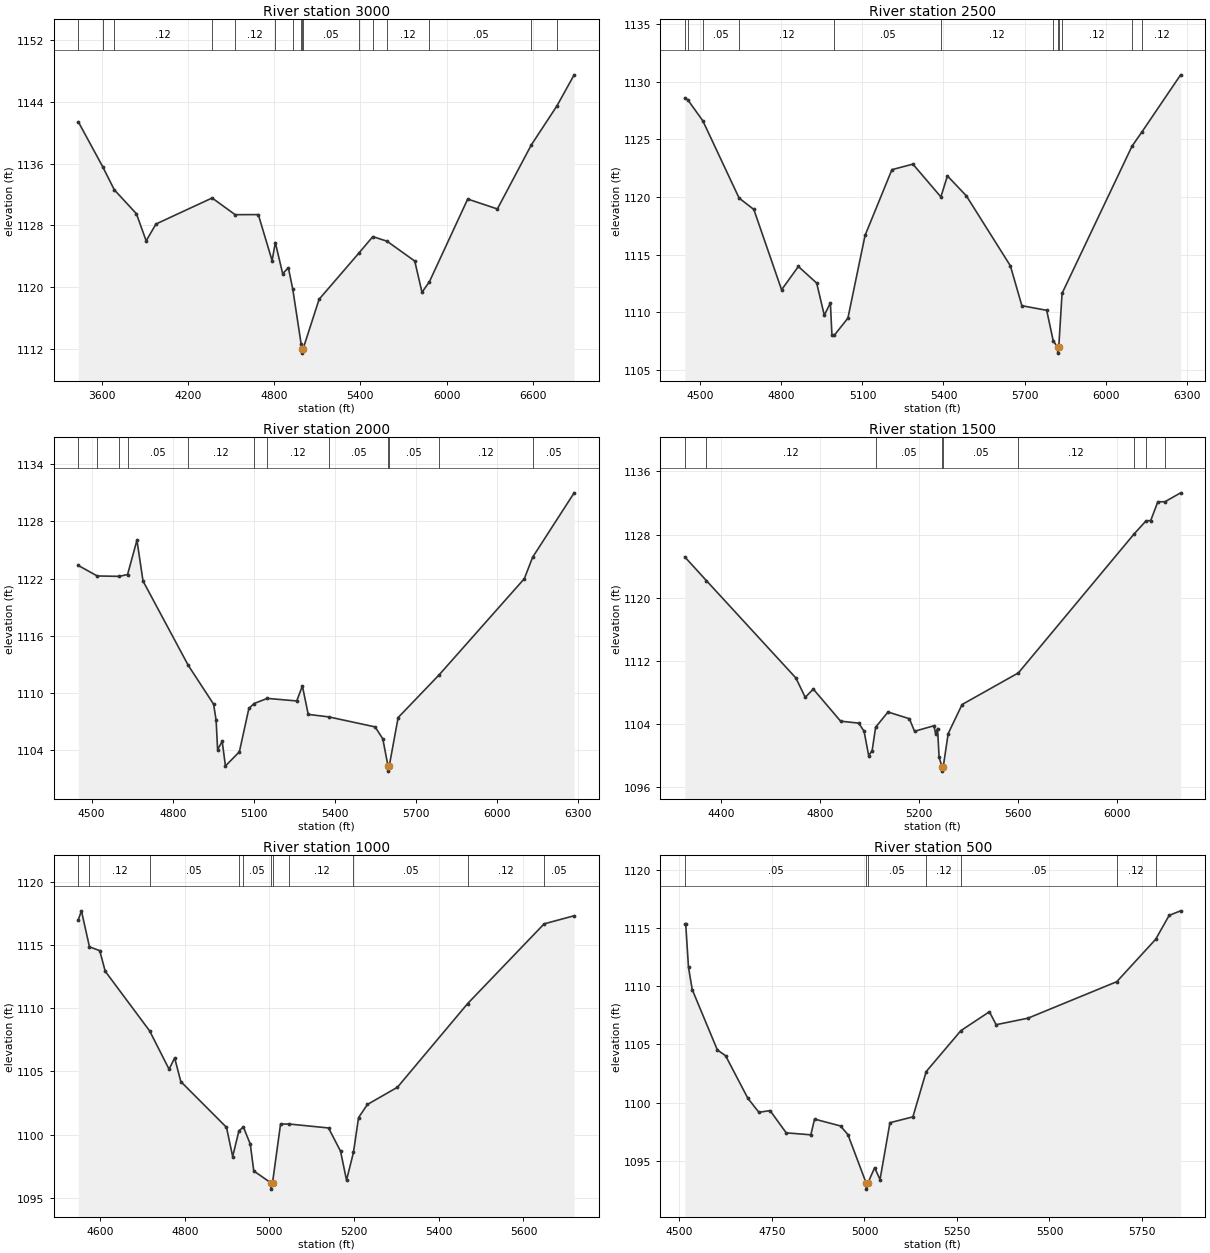
Type RM Length L Ch R = 1,3000,500,500,500
BEGIN DESCRIPTION:
SANFERNANDO061 6.0
END DESCRIPTION:
XS GIS Cut Line= 3
      2798305.67     10261053.12      2799713.44     10260375.18
      2799955.69     10258503.09
#Sta/Elev= 30
  3437.5 1141.40  3606.6 1135.61  3687.7 1132.61  3841.7 1129.51  3909.6 1126.00
  3977.5 1128.18  4368.6 1131.55  4528.7 1129.39  4689.9 1129.40  4785.9 1123.44
  4808.3 1125.79  4859.4 1121.76  4899.1 1122.52  4929.9 1119.73  4987.7 1112.68
  4996.5 1111.98  4996.7 1111.48  5000.5 1111.98  5113.0 1118.45  5388.2 1124.39
  5486.7 1126.55  5585.3 1125.96  5778.5 1123.39  5828.9 1119.35  5880.8 1120.73
  6147.0 1131.41  6353.3 1130.13  6589.5 1138.41  6767.4 1143.45  6887.7 1147.48
#Mann=16,-1,0
  3437.5    0.12       0  3606.6    0.05       0  3687.7    0.12       0
  4368.6    0.05       0  4528.7    0.12       0  4808.3    0.05       0
  4929.9    0.12       0  4987.7    0.05       0  4996.5    0.05       0
  5000.5    0.05       0  5388.2    0.12       0  5486.7    0.05       0
  5585.3    0.12       0  5880.8    0.05       0  6589.5    0.12       0
  6767.4    0.05       0
Bank Sta=4996.5,5000.5
Exp/Cntr=0.3,0.1

Type RM Length L Ch R = 1,2500,500,500,500
BEGIN DESCRIPTION:
SANFERNANDO061 5.0
END DESCRIPTION:
XS GIS Cut Line= 3
      2799655.68     10260753.11      2800157.60     10260510.00
      2801105.66     10259653.13
#Sta/Elev= 30
  4442.3 1128.59  4453.8 1128.41  4509.2 1126.60  4643.3 1119.91  4697.9 1118.92
  4800.6 1111.96  4862.8 1113.98  4930.6 1112.54  4958.7 1109.75  4981.3 1110.83
  4986.9 1108.07  4995.1 1108.00  5046.1 1109.50  5109.6 1116.67  5209.0 1122.37
  5286.7 1122.85  5390.4 1120.01  5414.5 1121.83  5484.7 1120.10  5647.6 1114.04
  5690.2 1110.58  5782.1 1110.18  5806.1 1107.55  5822.7 1106.97  5823.0 1106.47
  5826.7 1106.97  5839.0 1111.65  6097.8 1124.40  6135.5 1125.67  6277.9 1130.59
#Mann=12,-1,0
  4442.3    0.05       0  4453.8    0.12       0  4509.2    0.05       0
  4643.3    0.12       0  4995.1    0.05       0  5390.4    0.12       0
  5806.1    0.05       0  5822.7    0.05       0  5826.7    0.05       0
  5839.0    0.12       0  6097.8    0.05       0  6135.5    0.12       0
Bank Sta=5822.7,5826.7
Exp/Cntr=0.3,0.1

Type RM Length L Ch R = 1,2000,500,500,500
BEGIN DESCRIPTION:
SANFERNANDO061 4.0
END DESCRIPTION:
XS GIS Cut Line= 3
      2799955.70     10261053.10      2800449.40     10260812.50
      2801405.68     10259953.12
#Sta/Elev= 30
  4450.8 1123.37  4520.8 1122.27  4602.3 1122.23  4633.0 1122.42  4667.7 1126.02
  4690.2 1121.74  4857.5 1112.90  4951.4 1108.82  4960.7 1107.14  4966.2 1104.06
  4983.2 1104.92  4995.2 1102.34  5046.8 1103.83  5081.9 1108.37  5101.0 1108.89
  5150.1 1109.43  5259.0 1109.16  5280.0 1110.73  5301.6 1107.75  5377.3 1107.49
  5549.1 1106.44  5577.5 1105.19  5597.1 1102.30  5597.4 1101.80  5601.1 1102.30
  5634.3 1107.42  5785.4 1111.88  6101.4 1121.99  6131.9 1124.23  6285.7 1130.99
#Mann=12,-1,0
  4450.8    0.12       0  4520.8    0.05       0  4602.3    0.12       0
  4633.0    0.05       0  4857.5    0.12       0  5101.0    0.05       0
  5150.1    0.12       0  5377.3    0.05       0  5597.1    0.07       0
  5601.1    0.05       0  5785.4    0.12       0  6131.9    0.05       0
Bank Sta=5597.1,5601.1
Exp/Cntr=0.3,0.1

Type RM Length L Ch R = 1,1500,500,500,500
BEGIN DESCRIPTION:
SANFERNANDO061 3.0
END DESCRIPTION:
XS GIS Cut Line= 3
      2800055.68     10261253.11      2800767.16     10261030.13
      2801555.67     10260053.13
#Sta/Elev= 30
  4254.4 1125.17  4341.5 1122.17  4702.8 1109.83  4740.5 1107.38  4772.9 1108.43
  4883.2 1104.36  4956.5 1104.11  4978.0 1103.07  4996.6 1099.99  5010.5 1100.63
  5024.5 1103.59  5074.5 1105.52  5160.8 1104.67  5181.6 1103.08  5260.0 1103.78
  5266.4 1102.78  5274.4 1103.43  5280.8 1099.76  5293.2 1098.53  5293.4 1098.03
  5297.2 1098.53  5317.4 1102.79  5373.5 1106.47  5600.9 1110.48  6066.6 1128.04
  6115.9 1129.74  6134.8 1129.78  6163.5 1132.16  6192.2 1132.16  6255.5 1133.29
#Mann=9,-1,0
  4254.4    0.05       0  4341.5    0.12       0  5024.5    0.05       0
  5293.2    0.07       0  5297.2    0.05       0  5600.9    0.12       0
  6066.6    0.05       0  6115.9    0.12       0  6192.2    0.05       0
Bank Sta=5293.2,5297.2
Exp/Cntr=0.3,0.1

Type RM Length L Ch R = 1,1000,500,500,500
BEGIN DESCRIPTION:
SANFERNANDO061 2.0
END DESCRIPTION:
XS GIS Cut Line= 3
      2800505.65     10261603.14      2800863.66     10261328.37
      2801355.68     10260803.12
#Sta/Elev= 30
  4548.7 1117.01  4556.0 1117.71  4575.0 1114.86  4599.2 1114.56  4612.2 1112.93
  4717.1 1108.21  4763.0 1105.18  4776.2 1106.07  4790.7 1104.20  4898.6 1100.58
  4913.2 1098.27  4928.0 1100.31  4938.6 1100.60  4954.8 1099.25  4963.0 1097.13
  5003.3 1096.19  5003.6 1095.69  5007.3 1096.19  5026.3 1100.84  5047.0 1100.84
  5139.6 1100.53  5168.0 1098.69  5182.1 1096.40  5198.5 1098.60  5210.5 1101.35
  5231.5 1102.39  5302.3 1103.75  5468.1 1110.37  5648.8 1116.68  5719.7 1117.32
#Mann=11,-1,0
  4548.7    0.05       0  4575.0    0.12       0  4717.1    0.05       0
  4928.0    0.12       0  4938.6    0.05       0  5003.3    0.05       0
  5007.3    0.05       0  5047.0    0.12       0  5198.5    0.05       0
  5468.1    0.12       0  5648.8    0.05       0
Bank Sta=5003.3,5007.3
Exp/Cntr=0.3,0.1

Type RM Length L Ch R = 1,500,0,0,0
BEGIN DESCRIPTION:
SANFERNANDO061 1.0
END DESCRIPTION:
XS GIS Cut Line= 3
      2800655.65     10261653.11      2801140.32     10261679.83
      2801355.68     10260853.12
#Sta/Elev= 30
  4514.6 1115.32  4517.1 1115.32  4524.6 1111.61  4534.7 1109.70  4602.6 1104.52
  4624.8 1104.03  4684.9 1100.38  4714.9 1099.17  4745.0 1099.32  4788.6 1097.41
  4855.1 1097.24  4865.2 1098.59  4935.3 1098.00  4955.3 1097.26  5004.9 1093.08
  5005.2 1092.58  5008.9 1093.08  5027.6 1094.42  5042.1 1093.40  5068.9 1098.28
  5130.9 1098.78  5166.9 1102.67  5260.6 1106.18  5337.6 1107.80  5355.8 1106.69
  5442.0 1107.25  5681.8 1110.38  5786.9 1114.02  5823.3 1116.07  5854.3 1116.46
#Mann=7,-1,0
  4514.6    0.05       0  5004.9    0.05       0  5008.9    0.05       0
  5166.9    0.12       0  5260.6    0.05       0  5681.8    0.12       0
  5786.9    0.05       0
Bank Sta=5004.9,5008.9
Exp/Cntr=0.3,0.1

Chan Stop Cuts=-1