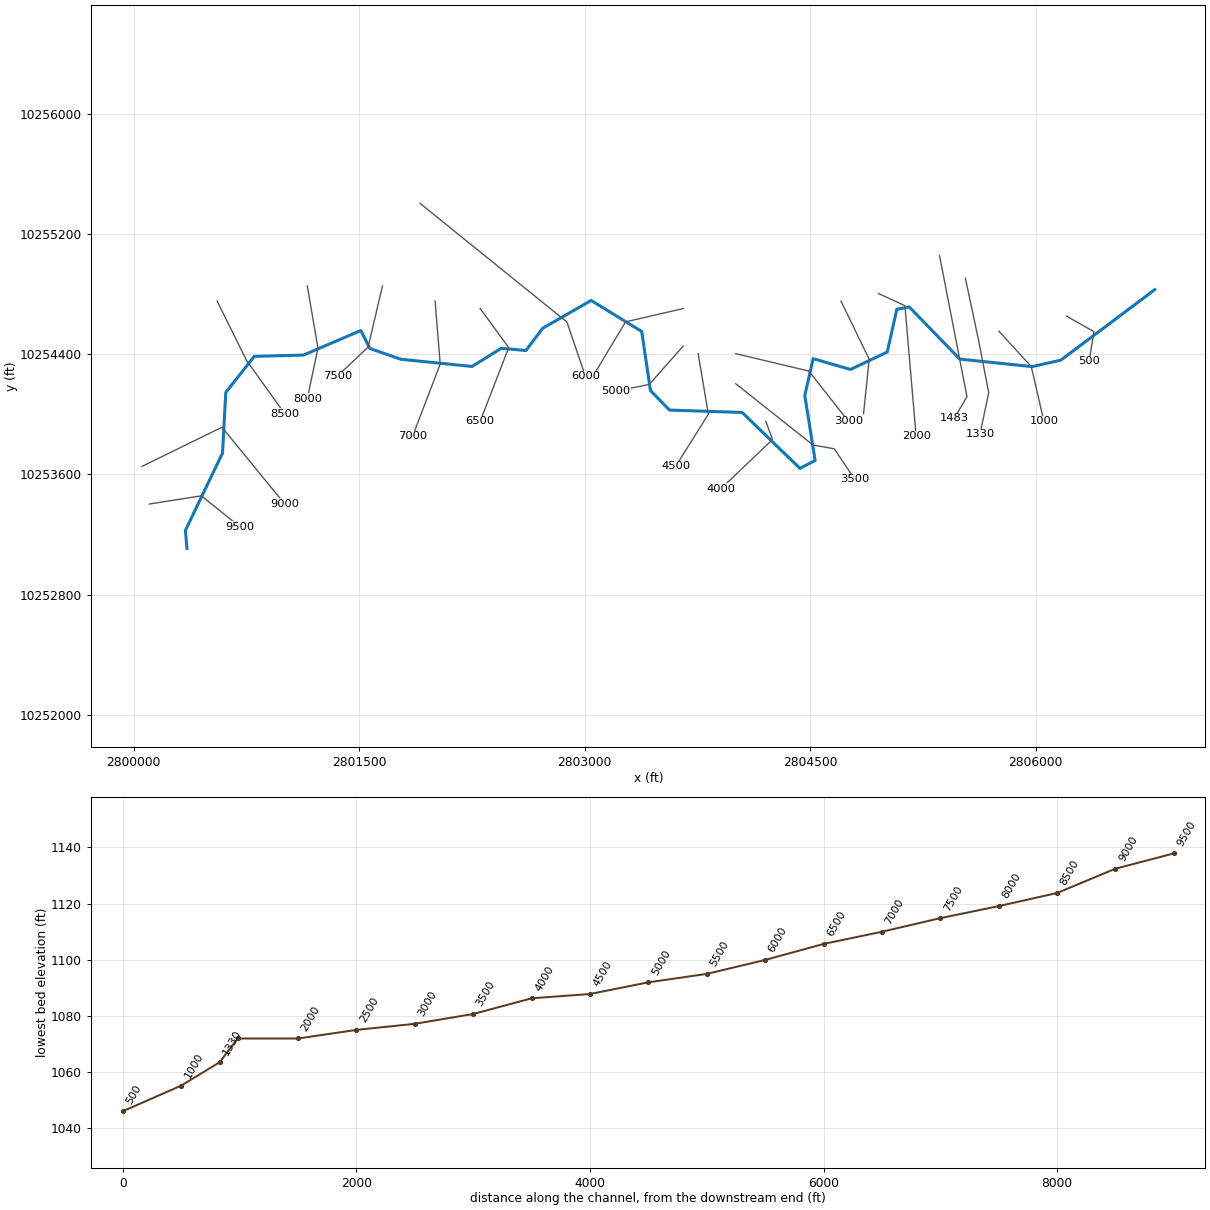
--- SANFERNANDO063.prj (project) ---

Proj Title=SANFERNANDO063 Base Level Engineering
Current Plan=p01
Default Exp/Contr=0.3,0.1
English Units
Geom File=g01
Flow File=f01
Plan File=p01
BEGIN DESCRIPTION:
SANFERNANDO063
END DESCRIPTION:

--- SANFERNANDO063.p01 (plan) ---

Plan Title=Multiple Run
Short Identifier=Multiple
Geom File=g01
Flow File=f01
Subcritical Flow
K Sum by GR= 0
Std Step Tol= 0.01
Critical Tol= 0.01
Num of Std Step Trials= 20
Max Error Tol= 0.3
Flow Tol Ratio= 0.001
Split Flow NTrial= 30
Split Flow Tol= 0.02
Split Flow Ratio= 0.02
Log Output Level= 0
Friction Slope Method= 1
Unsteady Friction Slope Method= 2
Unsteady Bridges Friction Slope Method= 1
Parabolic Critical Depth
Global Vel Dist=  1 , 1 , 1
Global Log Level= 0
CheckData=True
Encroach Param= -1, 0, 0, 0
BEGIN DESCRIPTION:
Multiple Run
END DESCRIPTION:

--- SANFERNANDO063.f01 (steady flow) ---

Flow Title=Multiple
Number of Profiles=7
Profile Names=10-year,25-year,50-year,1pct_min,100-year,1pct_plu,500-year
River Rch & RM= SANFERNANDO063,Reach-1,9500
     408     656     874     585    1159    2296    1589
River Rch & RM= SANFERNANDO063,Reach-1,3000
     506     831    1111     638    1491    3483    2057
Boundary for River Rch & Prof#=SANFERNANDO063,Reach-1,1
Up Type=0
Dn Type=3
Dn Slope=0.005
Boundary for River Rch & Prof#=SANFERNANDO063,Reach-1,2
Up Type=0
Dn Type=3
Dn Slope=0.005
Boundary for River Rch & Prof#=SANFERNANDO063,Reach-1,3
Up Type=0
Dn Type=3
Dn Slope=0.005
Boundary for River Rch & Prof#=SANFERNANDO063,Reach-1,4
Up Type=0
Dn Type=3
Dn Slope=0.005
Boundary for River Rch & Prof#=SANFERNANDO063,Reach-1,5
Up Type=0
Dn Type=3
Dn Slope=0.005
Boundary for River Rch & Prof#=SANFERNANDO063,Reach-1,6
Up Type=0
Dn Type=3
Dn Slope=0.005
Boundary for River Rch & Prof#=SANFERNANDO063,Reach-1,7
Up Type=0
Dn Type=3
Dn Slope=0.005

--- SANFERNANDO063.g01 (geometry) ---

Geom Title=Existing Conditions

River Reach=SANFERNANDO063,Reach-1
Reach XY= 30
      2800355.25     10253108.00      2800344.75     10253227.00
      2800591.75     10253742.00      2800613.50     10254145.00
      2800802.75     10254385.00      2801130.75     10254394.00
      2801512.00     10254557.00      2801571.50     10254438.00
      2801777.75     10254366.00      2802251.50     10254318.00
      2802446.50     10254439.00      2802609.75     10254424.00
      2802721.25     10254572.00      2803044.00     10254757.00
      2803380.00     10254551.00      2803438.25     10254158.00
      2803565.00     10254028.00      2804048.50     10254012.00
      2804433.00     10253640.00      2804533.75     10253693.00
      2804465.00     10254124.00      2804520.50     10254370.00
      2804769.00     10254298.00      2805013.50     10254414.00
      2805077.00     10254698.00      2805159.50     10254714.00
      2805496.25     10254367.00      2805977.25     10254317.00
      2806168.00     10254360.00      2806793.00     10254829.00

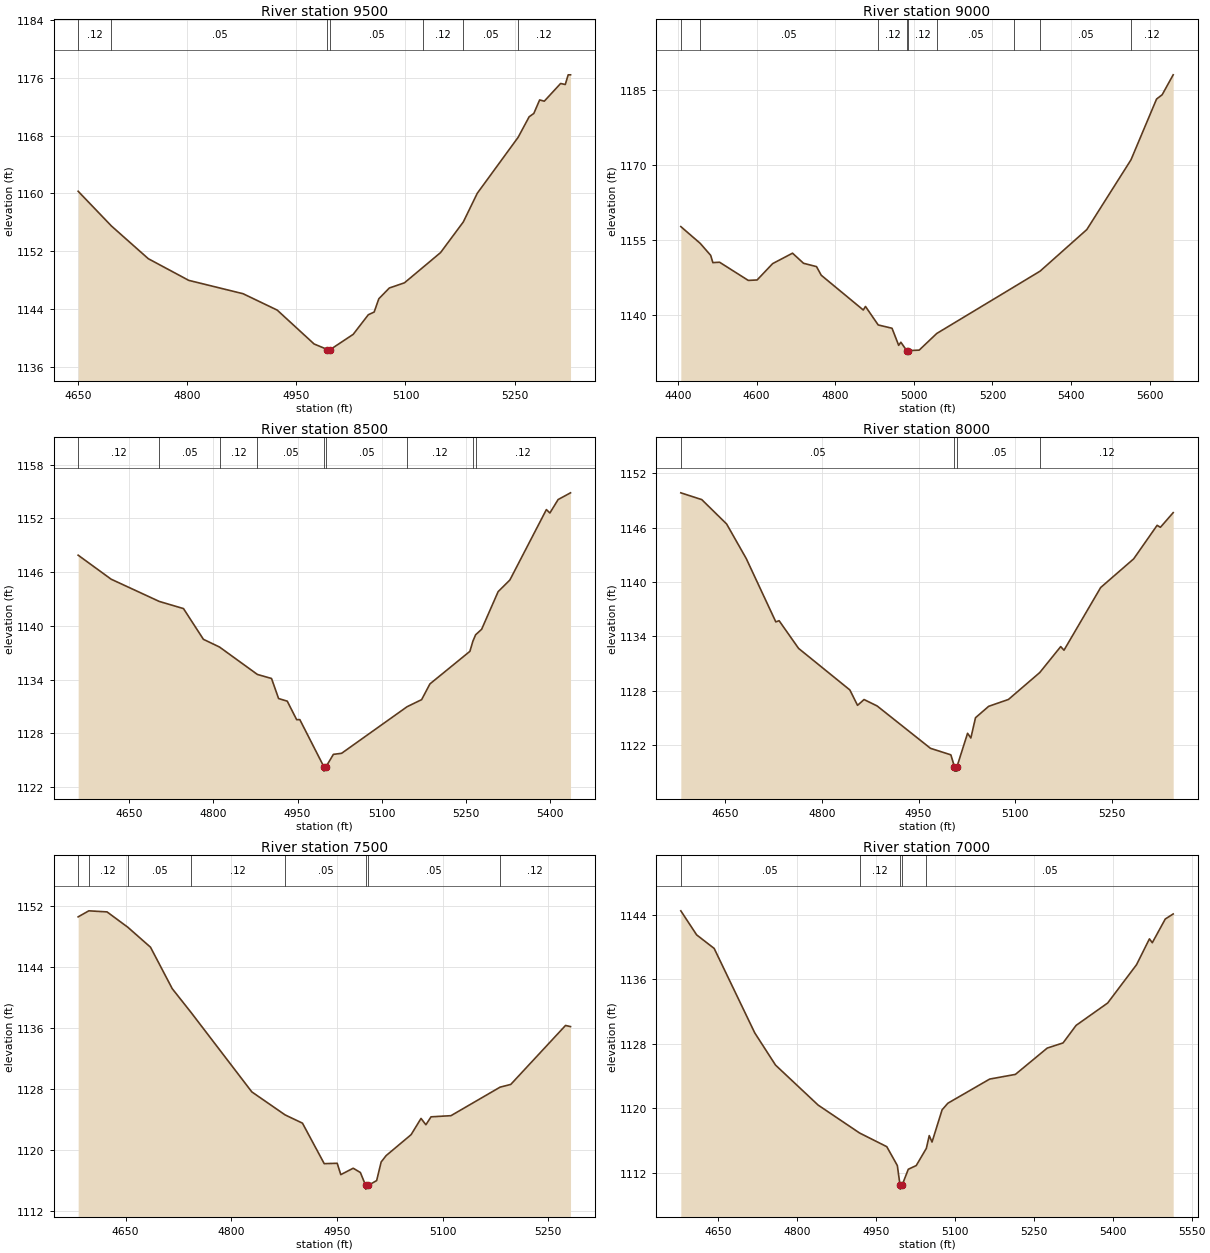
Type RM Length L Ch R = 1,9500,500,500,500
BEGIN DESCRIPTION:
SANFERNANDO063 19.0
END DESCRIPTION:
XS GIS Cut Line= 3
      2800105.68     10253403.11      2800450.83     10253457.43
      2800705.65     10253253.14
#Sta/Elev= 30
  4650.6 1160.28  4696.3 1155.47  4746.9 1150.94  4802.4 1147.94  4877.0 1146.09
  4923.9 1143.82  4974.5 1139.13  4992.8 1138.36  4993.0 1137.86  4996.5 1137.86
  4996.8 1138.36  5028.2 1140.46  5049.0 1143.18  5057.0 1143.55  5063.4 1145.39
  5077.8 1146.88  5098.6 1147.60  5123.5 1149.70  5148.2 1151.79  5179.4 1156.03
  5198.5 1159.99  5254.7 1167.76  5269.8 1170.60  5276.2 1171.06  5284.2 1172.93
  5290.6 1172.76  5313.0 1175.21  5319.4 1175.07  5323.4 1176.41  5326.6 1176.41
#Mann=7,-1,0
  4650.6    0.12       0  4696.3    0.05       0  4992.8    0.03       0
  4996.8    0.05       0  5123.5    0.12       0  5179.4    0.05       0
  5254.7    0.12       0
Bank Sta=4992.8,4996.8
Exp/Cntr=0.3,0.1

Type RM Length L Ch R = 1,9000,500,500,500
BEGIN DESCRIPTION:
SANFERNANDO063 18.0
END DESCRIPTION:
XS GIS Cut Line= 3
      2800055.70     10253653.12      2800587.91     10253913.73
      2801005.66     10253403.15
#Sta/Elev= 30
  4407.4 1157.75  4456.7 1154.40  4483.4 1151.99  4488.9 1150.54  4505.9 1150.62
  4579.0 1146.98  4601.5 1147.07  4640.9 1150.34  4691.5 1152.43  4719.5 1150.41
  4752.6 1149.74  4764.5 1148.02  4871.5 1141.06  4877.1 1141.77  4909.4 1138.07
  4944.6 1137.41  4961.5 1133.99  4967.1 1134.61  4982.0 1132.93  4982.3 1132.43
  4986.0 1132.93  5013.7 1133.03  5058.3 1136.36  5255.5 1145.71  5321.3 1148.84
  5440.1 1157.16  5552.4 1171.12  5617.4 1183.27  5631.7 1184.14  5659.7 1188.12
#Mann=9,-1,0
  4407.4    0.12       0  4456.7    0.05       0  4909.4    0.12       0
  4982.0    0.07       0  4986.0    0.12       0  5058.3    0.05       0
  5255.5    0.12       0  5321.3    0.05       0  5552.4    0.12       0
Bank Sta=4982,4986
Exp/Cntr=0.3,0.1

Type RM Length L Ch R = 1,8500,500,500,500
BEGIN DESCRIPTION:
SANFERNANDO063 17.0
END DESCRIPTION:
XS GIS Cut Line= 3
      2800555.70     10254753.08      2800751.72     10254358.04
      2801005.67     10254003.14
#Sta/Elev= 30
  4559.0 1147.88  4617.8 1145.20  4703.5 1142.72  4746.7 1141.92  4782.2 1138.49
  4810.9 1137.63  4878.4 1134.57  4903.6 1134.12  4916.2 1131.88  4931.6 1131.59
  4948.4 1129.52  4954.0 1129.53  4996.8 1124.28  4997.0 1123.78  5000.8 1124.28
  5013.8 1125.65  5028.5 1125.77  5145.2 1130.97  5171.1 1131.76  5185.8 1133.51
  5257.1 1137.15  5262.4 1138.28  5267.3 1139.00  5278.0 1139.61  5307.4 1143.81
  5328.3 1145.11  5393.4 1152.97  5399.6 1152.59  5414.3 1154.09  5436.4 1154.84
#Mann=9,-1,0
  4559.0    0.12       0  4703.5    0.05       0  4810.9    0.12       0
  4878.4    0.05       0  4996.8    0.03       0  5000.8    0.05       0
  5145.2    0.12       0  5262.4    0.05       0  5267.3    0.12       0
Bank Sta=4996.8,5000.8
Exp/Cntr=0.3,0.1

Type RM Length L Ch R = 1,8000,500,500,500
BEGIN DESCRIPTION:
SANFERNANDO063 16.0
END DESCRIPTION:
XS GIS Cut Line= 3
      2801155.68     10254853.11      2801226.64     10254440.47
      2801155.69     10254103.15
#Sta/Elev= 30
  4581.3 1149.86  4613.8 1149.11  4652.3 1146.42  4682.8 1142.59  4728.6 1135.60
  4733.7 1135.73  4763.9 1132.67  4843.4 1128.08  4855.3 1126.38  4865.4 1127.02
  4885.7 1126.31  4968.4 1121.63  5000.0 1120.91  5005.5 1119.61  5005.8 1119.11
  5009.3 1119.11  5009.5 1119.61  5025.9 1123.29  5031.0 1122.77  5038.2 1125.01
  5058.6 1126.27  5089.3 1127.03  5137.8 1130.00  5170.3 1132.87  5175.4 1132.47
  5232.3 1139.40  5283.4 1142.56  5319.8 1146.27  5324.9 1146.05  5344.7 1147.67
#Mann=4,-1,0
  4581.3    0.05       0  5005.5    0.05       0  5009.5    0.05       0
  5137.8    0.12       0
Bank Sta=5005.5,5009.5
Exp/Cntr=0.3,0.1

Type RM Length L Ch R = 1,7500,500,500,500
BEGIN DESCRIPTION:
SANFERNANDO063 15.0
END DESCRIPTION:
XS GIS Cut Line= 3
      2801655.67     10254853.06      2801559.97     10254446.78
      2801355.68     10254253.11
#Sta/Elev= 30
  4582.6 1150.53  4597.7 1151.32  4623.6 1151.18  4653.2 1149.16  4685.3 1146.55
  4716.1 1141.12  4742.9 1137.99  4829.1 1127.58  4876.4 1124.56  4901.0 1123.48
  4931.9 1118.17  4950.3 1118.22  4955.4 1116.73  4973.0 1117.57  4983.2 1117.01
  4990.6 1115.33  4990.9 1114.83  4994.6 1115.33  5006.3 1115.95  5012.7 1118.39
  5019.7 1119.22  5055.2 1121.97  5069.3 1124.10  5076.2 1123.27  5083.5 1124.31
  5111.8 1124.46  5181.5 1128.20  5196.7 1128.56  5274.4 1136.29  5281.5 1136.14
#Mann=8,-1,0
  4582.6    0.05       0  4597.7    0.12       0  4653.2    0.05       0
  4742.9    0.12       0  4876.4    0.05       0  4990.6    0.05       0
  4994.6    0.05       0  5181.5    0.12       0
Bank Sta=4990.6,4994.6
Exp/Cntr=0.3,0.1

Type RM Length L Ch R = 1,7000,500,500,500
BEGIN DESCRIPTION:
SANFERNANDO063 14.0
END DESCRIPTION:
XS GIS Cut Line= 3
      2802005.68     10254753.14      2802039.90     10254333.93
      2801855.68     10253853.11
#Sta/Elev= 30
  4579.4 1144.46  4609.5 1141.48  4642.8 1139.80  4719.9 1129.34  4759.4 1125.35
  4840.3 1120.40  4919.1 1116.94  4970.7 1115.25  4990.8 1112.91  4995.9 1110.49
  4996.2 1109.99  4999.9 1110.49  5011.6 1112.45  5026.7 1112.91  5045.9 1115.04
  5051.4 1116.62  5056.7 1115.82  5075.8 1119.81  5086.8 1120.63  5166.2 1123.62
  5215.1 1124.20  5275.6 1127.46  5305.7 1128.10  5330.4 1130.27  5390.4 1133.04
  5445.2 1137.78  5469.8 1140.99  5475.2 1140.51  5499.9 1143.45  5514.9 1144.07
#Mann=5,-1,0
  4579.4    0.05       0  4919.1    0.12       0  4995.9    0.07       0
  4999.9    0.12       0  5045.9    0.05       0
Bank Sta=4995.9,4999.9
Exp/Cntr=0.3,0.1

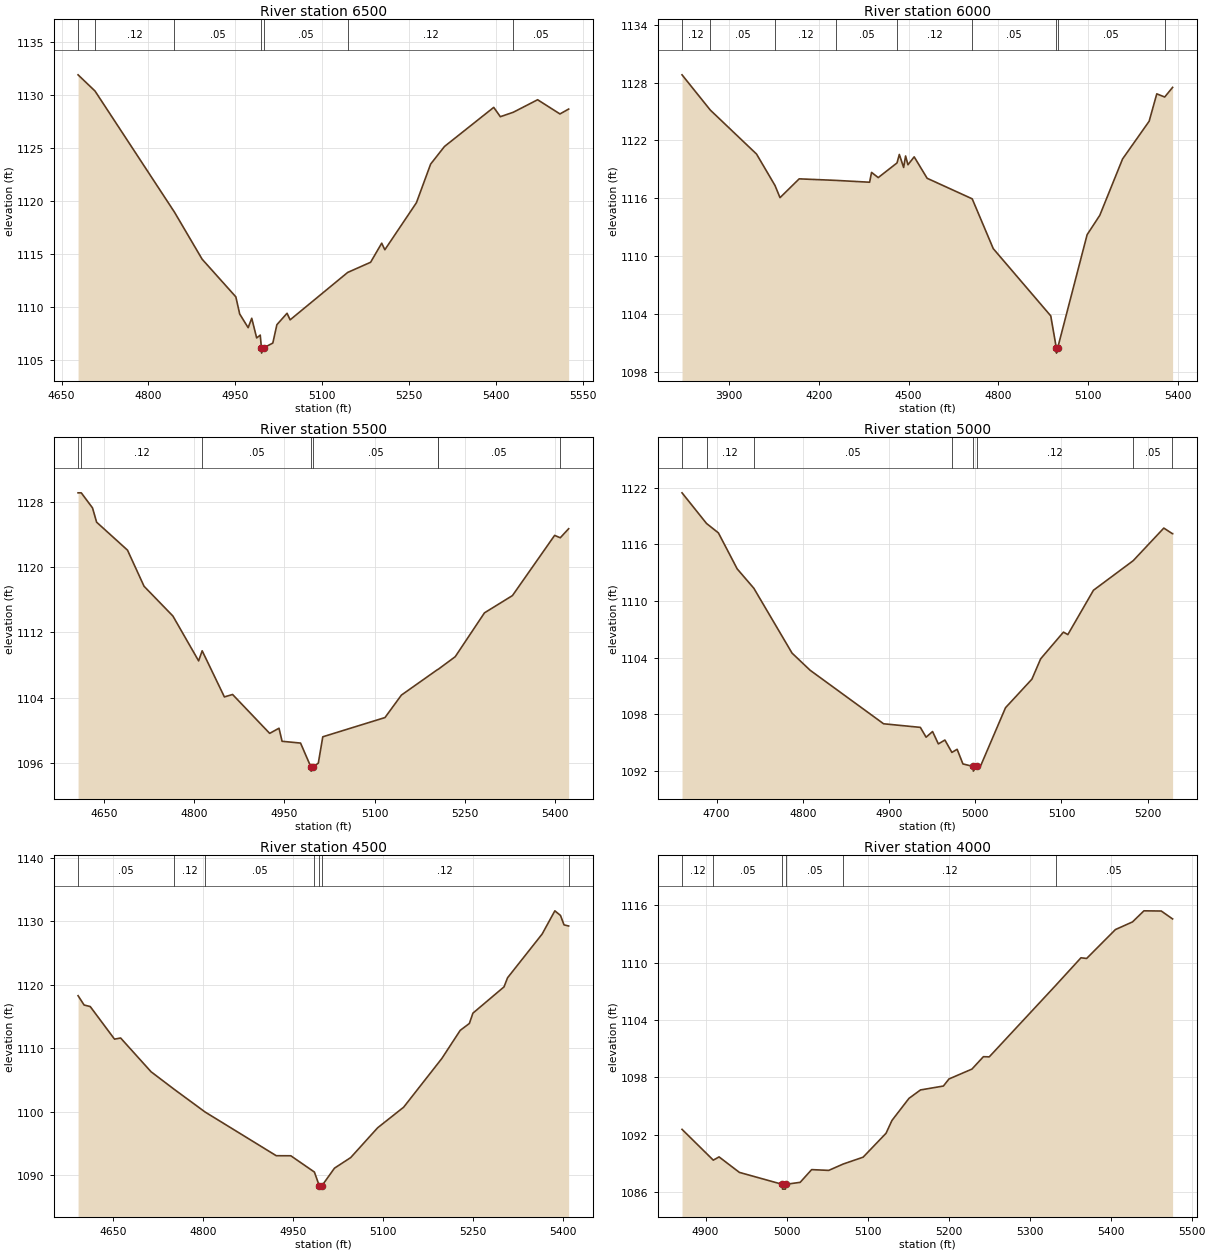
Type RM Length L Ch R = 1,6500,500,500,500
BEGIN DESCRIPTION:
SANFERNANDO063 13.0
END DESCRIPTION:
XS GIS Cut Line= 3
      2802305.68     10254703.11      2802495.43     10254443.46
      2802305.68     10253953.09
#Sta/Elev= 30
  4678.4 1131.90  4707.7 1130.37  4844.9 1118.95  4892.7 1114.51  4950.9 1110.96
  4957.6 1109.34  4972.2 1108.05  4978.4 1108.94  4986.9 1107.08  4993.1 1107.35
  4995.1 1106.15  4995.4 1105.65  4999.1 1106.15  5014.8 1106.60  5021.8 1108.33
  5039.4 1109.41  5044.7 1108.79  5144.1 1113.26  5183.7 1114.22  5202.9 1116.02
  5208.3 1115.40  5262.8 1119.83  5287.4 1123.48  5311.3 1125.14  5396.4 1128.83
  5407.8 1127.95  5430.2 1128.37  5472.2 1129.55  5510.8 1128.21  5525.8 1128.67
#Mann=7,-1,0
  4678.4    0.05       0  4707.7    0.12       0  4844.9    0.05       0
  4995.1    0.03       0  4999.1    0.05       0  5144.1    0.12       0
  5430.2    0.05       0
Bank Sta=4995.1,4999.1
Exp/Cntr=0.3,0.1

Type RM Length L Ch R = 1,6000,500,500,500
BEGIN DESCRIPTION:
SANFERNANDO063 12.0
END DESCRIPTION:
XS GIS Cut Line= 3
      2801905.71     10255403.09      2802882.57     10254613.77
      2803005.69     10254253.10
#Sta/Elev= 30
  3744.1 1128.80  3838.4 1125.15  3992.7 1120.59  4054.4 1117.33  4071.1 1116.07
  4135.0 1118.02  4258.3 1117.86  4370.1 1117.67  4376.5 1118.69  4398.8 1118.15
  4461.5 1119.67  4469.2 1120.55  4483.6 1119.20  4490.1 1120.39  4498.0 1119.48
  4518.8 1120.30  4562.0 1118.08  4712.4 1115.95  4782.6 1110.79  4974.5 1103.82
  4993.3 1100.46  4993.6 1099.96  4997.3 1100.46  5095.8 1112.23  5138.1 1114.24
  5214.1 1120.08  5302.8 1123.99  5328.3 1126.83  5354.7 1126.50  5381.1 1127.50
#Mann=9,-1,0
  3744.1    0.12       0  3838.4    0.05       0  4054.4    0.12       0
  4258.3    0.05       0  4461.5    0.12       0  4712.4    0.05       0
  4993.3    0.03       0  4997.3    0.05       0  5354.7    0.12       0
Bank Sta=4993.3,4997.3
Exp/Cntr=0.3,0.1

Type RM Length L Ch R = 1,5500,500,500,500
BEGIN DESCRIPTION:
SANFERNANDO063 11.0
END DESCRIPTION:
XS GIS Cut Line= 3
      2803655.73     10254703.12      2803273.17     10254614.91
      2803055.70     10254253.14
#Sta/Elev= 30
  4607.4 1129.12  4612.7 1129.12  4631.4 1127.27  4638.2 1125.52  4689.5 1122.09
  4717.0 1117.66  4764.9 1114.01  4807.6 1108.51  4813.5 1109.75  4850.4 1104.09
  4864.0 1104.39  4925.6 1099.62  4941.1 1100.25  4946.2 1098.65  4976.9 1098.43
  4994.1 1095.49  4994.4 1094.99  4998.1 1095.49  5006.4 1095.98  5013.8 1099.20
  5117.1 1101.56  5144.3 1104.31  5204.5 1107.45  5205.7 1107.49  5233.7 1109.02
  5282.3 1114.40  5328.8 1116.52  5398.8 1123.90  5408.2 1123.61  5422.1 1124.72
#Mann=8,-1,0
  4607.4    0.05       0  4612.7    0.12       0  4813.5    0.05       0
  4994.1    0.05       0  4998.1    0.05       0  5204.5    0.12       0
  5205.7    0.05       0  5408.2    0.12       0
Bank Sta=4994.1,4998.1
Exp/Cntr=0.3,0.1

Type RM Length L Ch R = 1,5000,500,500,500
BEGIN DESCRIPTION:
SANFERNANDO063 10.0
END DESCRIPTION:
XS GIS Cut Line= 3
      2803655.69     10254453.12      2803430.04     10254198.67
      2803205.71     10254153.12
#Sta/Elev= 30
  4659.9 1121.45  4688.3 1118.21  4702.1 1117.21  4723.9 1113.40  4743.2 1111.35
  4787.5 1104.49  4808.4 1102.68  4893.7 1097.01  4936.3 1096.63  4943.0 1095.59
  4950.5 1096.19  4957.2 1094.88  4964.8 1095.29  4972.9 1093.98  4979.0 1094.31
  4985.7 1092.76  4997.5 1092.50  4997.8 1092.00  5001.5 1092.50  5006.2 1092.55
  5035.1 1098.71  5065.7 1101.73  5075.9 1103.89  5102.3 1106.71  5107.4 1106.45
  5137.1 1111.14  5183.2 1114.27  5218.7 1117.72  5228.6 1117.13  5228.9 1117.13
#Mann=8,-1,0
  4659.9    0.05       0  4688.3    0.12       0  4743.2    0.05       0
  4972.9    0.12       0  4997.5    0.07       0  5001.5    0.12       0
  5183.2    0.05       0  5228.6    0.12       0
Bank Sta=4997.5,5001.5
Exp/Cntr=0.3,0.1

Type RM Length L Ch R = 1,4500,500,500,500
BEGIN DESCRIPTION:
SANFERNANDO063 9.0
END DESCRIPTION:
XS GIS Cut Line= 3
      2803755.69     10254403.09      2803823.43     10254000.24
      2803605.67     10253653.09
#Sta/Elev= 30
  4591.5 1118.29  4601.6 1116.82  4611.8 1116.58  4652.3 1111.45  4662.5 1111.63
  4713.2 1106.32  4752.3 1103.52  4803.4 1099.98  4922.1 1093.10  4946.4 1093.09
  4985.7 1090.53  4994.0 1088.34  4994.3 1087.84  4998.0 1088.34  5019.2 1091.14
  5046.3 1092.81  5091.1 1097.49  5134.6 1100.74  5198.3 1108.41  5228.9 1112.83
  5244.2 1113.92  5250.1 1115.54  5302.0 1119.68  5307.9 1121.11  5365.6 1128.00
  5386.8 1131.65  5396.2 1130.92  5402.1 1129.44  5409.7 1129.26  5409.8 1129.26
#Mann=7,-1,0
  4591.5    0.05       0  4752.3    0.12       0  4803.4    0.05       0
  4985.7    0.12       0  4994.0    0.07       0  4998.0    0.12       0
  5409.7    0.05       0
Bank Sta=4994,4998
Exp/Cntr=0.3,0.1

Type RM Length L Ch R = 1,4000,500,500,500
BEGIN DESCRIPTION:
SANFERNANDO063 8.0
END DESCRIPTION:
XS GIS Cut Line= 3
      2804205.67     10253953.14      2804250.37     10253832.13
      2803905.69     10253503.12
#Sta/Elev= 30
  4871.0 1092.56  4909.6 1089.34  4916.7 1089.68  4941.8 1088.06  4994.8 1086.81
  4995.1 1086.31  4998.6 1086.31  4998.8 1086.81  5016.8 1087.02  5031.0 1088.35
  5052.1 1088.27  5070.1 1088.94  5094.5 1089.65  5122.8 1092.15  5130.1 1093.49
  5151.1 1095.80  5165.3 1096.68  5193.6 1097.09  5200.5 1097.83  5228.8 1098.86
  5243.0 1100.16  5250.2 1100.14  5332.3 1107.62  5363.4 1110.50  5370.4 1110.43
  5405.9 1113.45  5427.0 1114.25  5441.1 1115.41  5462.5 1115.39  5476.5 1114.56
#Mann=6,-1,0
  4871.0    0.12       0  4909.6    0.05       0  4994.8    0.05       0
  4998.8    0.05       0  5070.1    0.12       0  5332.3    0.05       0
Bank Sta=4994.8,4998.8
Exp/Cntr=0.3,0.1

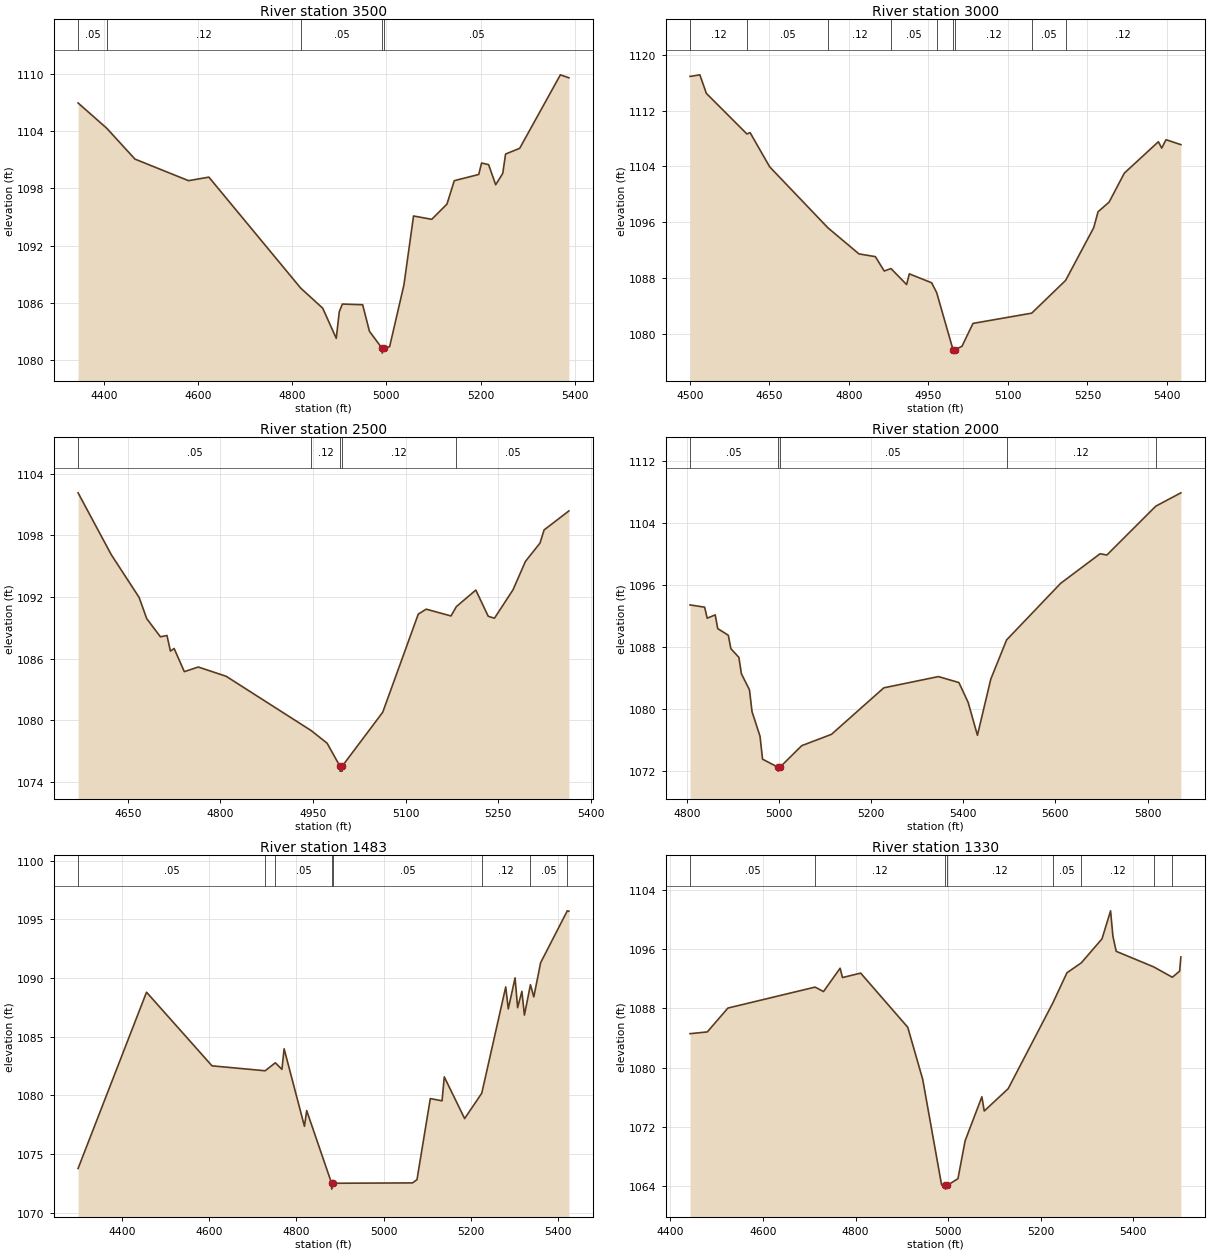
Type RM Length L Ch R = 1,3500,500,500,500
BEGIN DESCRIPTION:
SANFERNANDO063 7.0
END DESCRIPTION:
XS GIS Cut Line= 4
      2804005.72     10254203.08      2804519.04     10253795.74
      2804661.24     10253770.13      2804796.79     10253568.07
#Sta/Elev= 30
  4344.7 1106.94  4405.5 1104.30  4465.6 1101.06  4579.4 1098.80  4622.7 1099.17
  4817.7 1087.55  4864.6 1085.44  4893.4 1082.28  4899.8 1085.07  4906.4 1085.87
  4949.5 1085.80  4963.9 1083.02  4990.8 1081.23  4991.0 1080.73  4994.8 1081.23
  5006.8 1081.41  5037.2 1087.88  5057.6 1095.10  5096.3 1094.75  5128.7 1096.35
  5144.2 1098.80  5196.2 1099.45  5202.2 1100.65  5217.2 1100.48  5232.2 1098.37
  5247.2 1099.56  5253.2 1101.59  5283.2 1102.19  5369.7 1109.89  5387.8 1109.58
#Mann=5,-1,0
  4344.7    0.05       0  4405.5    0.12       0  4817.7    0.05       0
  4990.8    0.03       0  4994.8    0.05       0
Bank Sta=4990.8,4994.8
Exp/Cntr=0.3,0.1

Type RM Length L Ch R = 1,3000,500,500,500
BEGIN DESCRIPTION:
SANFERNANDO063 6.0
END DESCRIPTION:
XS GIS Cut Line= 3
      2804005.68     10254403.11      2804491.63     10254287.58
      2804755.66     10253953.14
#Sta/Elev= 30
  4500.5 1116.90  4519.0 1117.13  4531.3 1114.47  4607.8 1108.65  4613.7 1108.85
  4650.7 1103.94  4760.5 1095.20  4819.1 1091.46  4850.0 1091.07  4866.7 1089.01
  4879.4 1089.36  4908.9 1087.07  4914.0 1088.60  4956.2 1087.32  4965.7 1085.89
  4996.4 1077.74  4996.6 1077.24  5000.4 1077.74  5013.3 1078.22  5034.1 1081.50
  5144.8 1082.97  5208.7 1087.66  5261.8 1095.23  5269.9 1097.50  5290.7 1098.88
  5319.5 1103.04  5383.7 1107.54  5390.0 1106.63  5398.1 1107.83  5426.1 1107.12
#Mann=9,-1,0
  4500.5    0.12       0  4607.8    0.05       0  4760.5    0.12       0
  4879.4    0.05       0  4965.7    0.12       0  4996.4    0.07       0
  5000.4    0.12       0  5144.8    0.05       0  5208.7    0.12       0
Bank Sta=4996.4,5000.4
Exp/Cntr=0.3,0.1

Type RM Length L Ch R = 1,2500,500,500,500
BEGIN DESCRIPTION:
SANFERNANDO063 5.0
END DESCRIPTION:
XS GIS Cut Line= 3
      2804705.66     10254753.15      2804893.42     10254365.87
      2804855.69     10254003.12
#Sta/Elev= 30
  4569.6 1102.15  4623.3 1096.14  4668.5 1091.97  4680.8 1089.91  4703.0 1088.14
  4713.6 1088.27  4719.2 1086.75  4725.2 1087.00  4741.7 1084.75  4764.3 1085.20
  4809.5 1084.30  4947.1 1079.02  4973.0 1077.79  4993.6 1075.57  4993.9 1075.07
  4997.4 1075.07  4997.7 1075.57  5063.1 1080.80  5120.7 1090.35  5133.5 1090.83
  5173.7 1090.17  5182.4 1091.08  5213.9 1092.69  5234.0 1090.14  5244.1 1089.95
  5274.2 1092.72  5294.3 1095.48  5317.9 1097.26  5324.5 1098.54  5364.7 1100.39
#Mann=5,-1,0
  4569.6    0.05       0  4947.1    0.12       0  4993.6    0.07       0
  4997.7    0.12       0  5182.4    0.05       0
Bank Sta=4993.6,4997.7
Exp/Cntr=0.3,0.1

Type RM Length L Ch R = 1,2000,517,517,517
BEGIN DESCRIPTION:
SANFERNANDO063 4.0
END DESCRIPTION:
XS GIS Cut Line= 3
      2804955.66     10254803.12      2805130.99     10254722.21
      2805205.68     10253853.11
#Sta/Elev= 30
  4806.9 1093.43  4838.6 1093.14  4844.1 1091.72  4861.5 1092.15  4867.0 1090.38
  4890.0 1089.52  4895.5 1087.80  4912.9 1086.67  4918.4 1084.56  4935.9 1082.49
  4941.4 1079.69  4958.8 1076.51  4964.3 1073.56  4997.8 1072.52  4998.0 1072.02
  5001.9 1072.52  5049.3 1075.30  5113.9 1076.76  5227.5 1082.75  5346.1 1084.20
  5390.5 1083.43  5410.6 1080.87  5430.7 1076.64  5459.7 1083.87  5494.0 1088.92
  5611.3 1096.21  5696.9 1100.02  5711.7 1099.86  5817.8 1106.15  5872.3 1107.87
#Mann=5,-1,0
  4806.9    0.05       0  4997.8    0.03       0  5001.9    0.05       0
  5494.0    0.12       0  5817.8    0.05       0
Bank Sta=4997.8,5001.9
Exp/Cntr=0.3,0.1

Type RM Length L Ch R = 1,1483,153,153,153
BEGIN DESCRIPTION:
Mapping XS 790c0f92
END DESCRIPTION:
XS GIS Cut Line= 3
      2805361.39     10255055.23      2805543.73     10254116.70
      2805457.92     10253971.89
#Sta/Elev= 30
  4299.8 1073.78  4456.6 1088.79  4606.6 1082.52  4728.3 1082.10  4751.7 1082.78
  4766.7 1082.22  4771.8 1083.97  4818.4 1077.37  4823.5 1078.71  4880.6 1072.52
  4880.8 1072.02  4884.7 1072.52  5066.0 1072.55  5076.2 1072.83  5106.7 1079.73
  5133.6 1079.54  5138.7 1081.58  5185.3 1078.03  5224.6 1080.19  5279.5 1089.24
  5285.3 1087.37  5300.9 1090.01  5306.7 1087.47  5316.5 1088.86  5322.3 1086.84
  5336.1 1089.43  5343.8 1088.39  5359.4 1091.30  5420.5 1095.72  5424.2 1095.69
#Mann=8,-1,0
  4299.8    0.05       0  4728.3    0.12       0  4751.7    0.05       0
  4880.6    0.03       0  4884.7    0.05       0  5224.6    0.12       0
  5336.1    0.05       0  5420.5    0.12       0
Bank Sta=4880.6,4884.7
Exp/Cntr=0.3,0.1

Type RM Length L Ch R = 1,1330,330,330,330
BEGIN DESCRIPTION:
Mapping XS 24b908e7
END DESCRIPTION:
XS GIS Cut Line= 4
      2805533.00     10254905.12      2805618.82     10254502.85
      2805688.54     10254143.52      2805629.92     10253866.40
#Sta/Elev= 30
  4442.4 1084.59  4479.7 1084.83  4524.2 1088.05  4712.6 1090.88  4730.8 1090.28
  4766.7 1093.43  4771.8 1092.17  4811.1 1092.77  4912.8 1085.46  4945.1 1078.44
  4985.9 1064.18  4994.0 1064.10  4994.3 1063.60  4998.1 1064.10  5021.3 1065.01
  5036.8 1070.13  5073.0 1076.07  5078.1 1074.15  5129.8 1077.16  5226.0 1088.70
  5256.8 1092.81  5287.9 1094.16  5332.6 1097.40  5351.1 1101.18  5356.2 1097.74
  5363.3 1095.71  5444.3 1093.61  5484.6 1092.21  5500.3 1093.04  5503.0 1094.95
#Mann=8,-1,0
  4442.4    0.05       0  4712.6    0.12       0  4994.0    0.07       0
  4998.1    0.12       0  5226.0    0.05       0  5287.9    0.12       0
  5444.3    0.05       0  5484.6    0.12       0
Bank Sta=4994,4998.1
Exp/Cntr=0.3,0.1

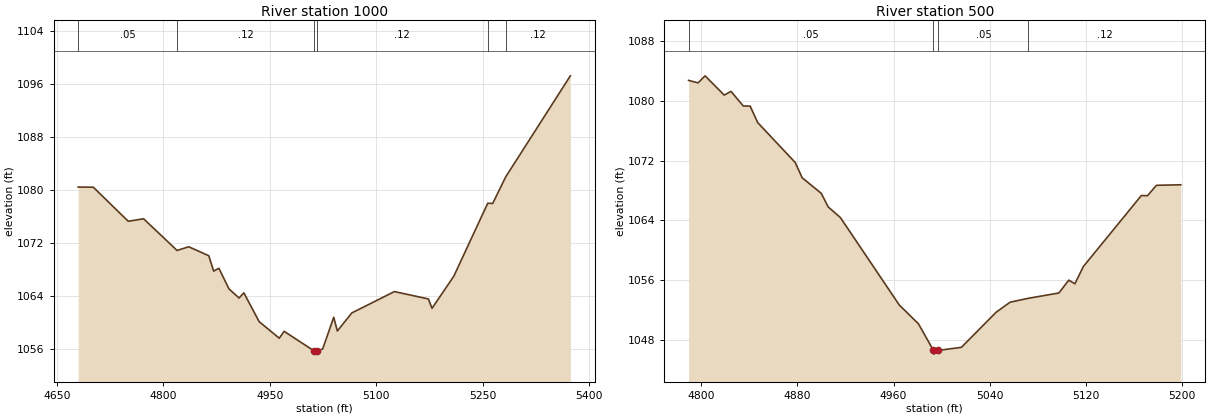
Type RM Length L Ch R = 1,1000,500,500,500
BEGIN DESCRIPTION:
SANFERNANDO063 2.0
END DESCRIPTION:
XS GIS Cut Line= 3
      2805755.66     10254553.14      2805971.61     10254317.00
      2806055.69     10253953.09
#Sta/Elev= 30
  4680.0 1080.45  4701.3 1080.43  4750.6 1075.29  4772.2 1075.67  4819.4 1070.89
  4835.8 1071.45  4864.1 1070.09  4870.9 1067.78  4878.3 1068.20  4892.5 1065.10
  4906.7 1063.72  4913.5 1064.50  4935.0 1060.16  4963.4 1057.66  4970.2 1058.70
  5012.2 1055.76  5012.5 1055.26  5016.4 1055.76  5024.5 1056.03  5040.1 1060.82
  5045.2 1058.75  5065.6 1061.47  5125.6 1064.69  5173.5 1063.58  5178.6 1062.17
  5209.3 1067.01  5257.1 1078.01  5264.1 1077.98  5282.4 1081.98  5373.5 1097.22
#Mann=6,-1,0
  4680.0    0.05       0  4819.4    0.12       0  5012.2    0.07       0
  5016.4    0.12       0  5257.1    0.05       0  5282.4    0.12       0
Bank Sta=5012.2,5016.4
Exp/Cntr=0.3,0.1

Type RM Length L Ch R = 1,500,0,0,0
BEGIN DESCRIPTION:
SANFERNANDO063 1.0
END DESCRIPTION:
XS GIS Cut Line= 3
      2806205.68     10254653.11      2806388.82     10254549.33
      2806355.68     10254353.11
#Sta/Elev= 30
  4789.5 1082.72  4797.4 1082.39  4803.2 1083.33  4819.1 1080.76  4824.8 1081.25
  4835.0 1079.30  4840.7 1079.29  4847.0 1077.08  4878.2 1071.75  4884.0 1069.71
  4899.9 1067.62  4905.6 1065.82  4915.8 1064.39  4964.8 1052.70  4980.7 1050.20
  4993.2 1046.64  4993.5 1046.14  4997.4 1046.64  5016.5 1047.05  5045.3 1051.73
  5057.0 1053.08  5072.1 1053.60  5097.6 1054.31  5105.8 1056.03  5110.9 1055.54
  5117.9 1057.84  5166.2 1067.34  5171.3 1067.31  5178.7 1068.70  5199.0 1068.77
#Mann=4,-1,0
  4789.5    0.05       0  4993.2    0.03       0  4997.4    0.05       0
  5072.1    0.12       0
Bank Sta=4993.2,4997.4
Exp/Cntr=0.3,0.1

Chan Stop Cuts=-1