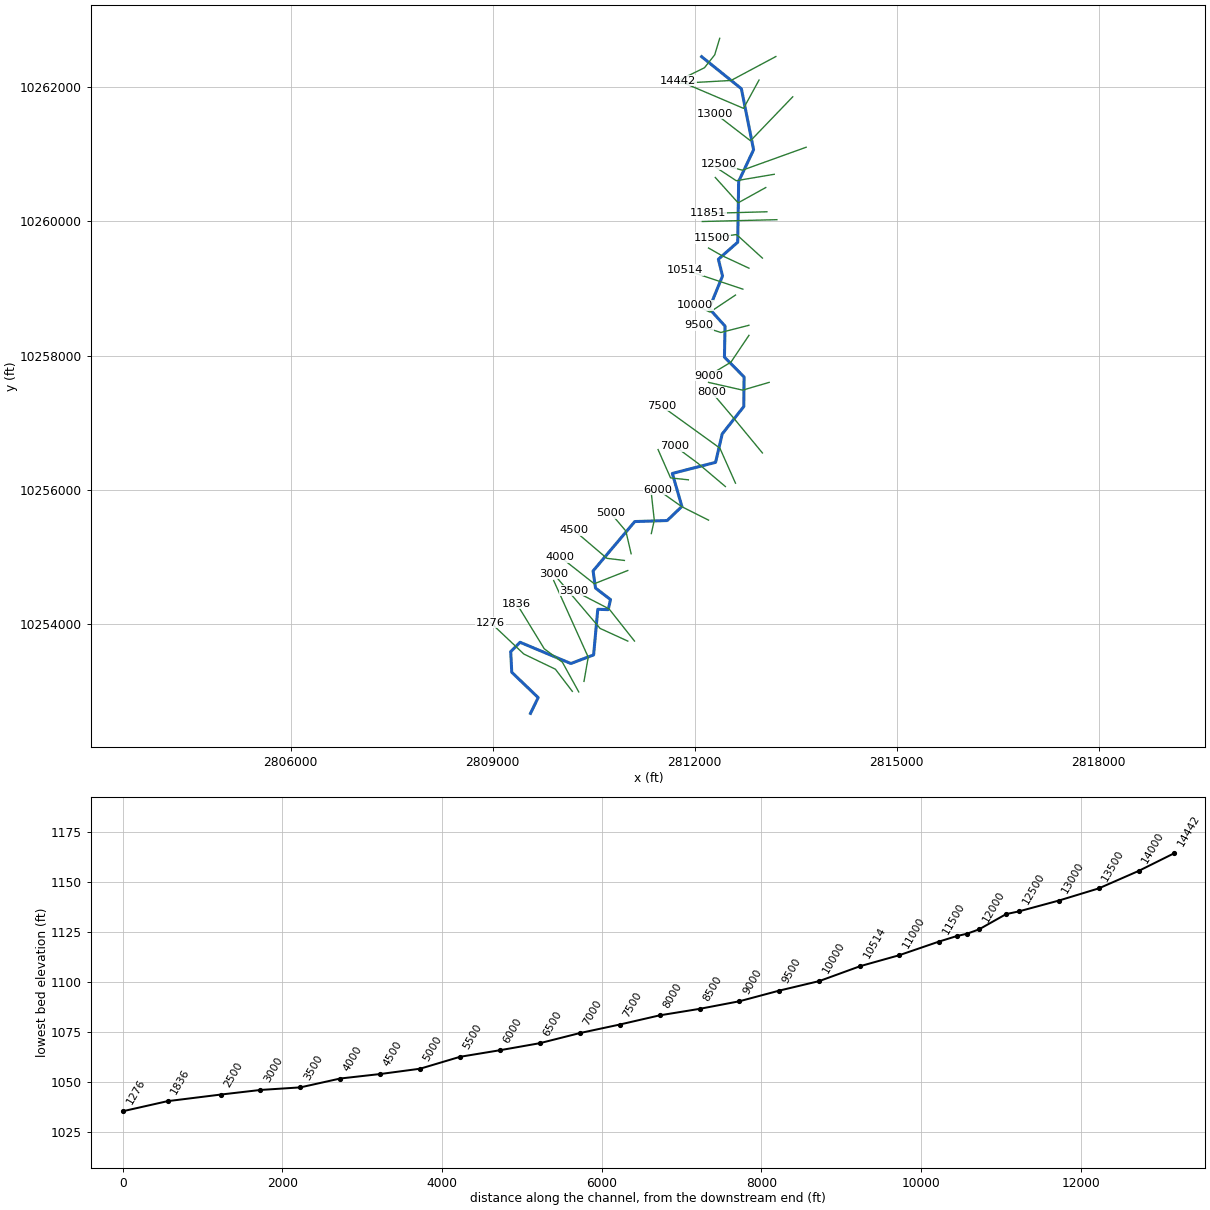
--- SANFERNANDO064.prj (project) ---

Proj Title=SANFERNANDO064 Base Level Engineering
Current Plan=p01
Default Exp/Contr=0.3,0.1
English Units
Geom File=g01
Flow File=f01
Plan File=p01
BEGIN DESCRIPTION:
SANFERNANDO064
END DESCRIPTION:

--- SANFERNANDO064.p01 (plan) ---

Plan Title=Multiple Run
Short Identifier=Multiple
Geom File=g01
Flow File=f01
Subcritical Flow
K Sum by GR= 0
Std Step Tol= 0.01
Critical Tol= 0.01
Num of Std Step Trials= 20
Max Error Tol= 0.3
Flow Tol Ratio= 0.001
Split Flow NTrial= 30
Split Flow Tol= 0.02
Split Flow Ratio= 0.02
Log Output Level= 0
Friction Slope Method= 1
Unsteady Friction Slope Method= 2
Unsteady Bridges Friction Slope Method= 1
Parabolic Critical Depth
Global Vel Dist=  1 , 1 , 1
Global Log Level= 0
CheckData=True
Encroach Param= -1, 0, 0, 0
BEGIN DESCRIPTION:
Multiple Run
END DESCRIPTION:

--- SANFERNANDO064.f01 (steady flow) ---

Flow Title=Multiple
Number of Profiles=7
Profile Names=10-year,25-year,50-year,1pct_min,100-year,1pct_plu,500-year
River Rch & RM= SANFERNANDO064,Reach-1,14442
     413     666     881     566    1170    2416    1603
River Rch & RM= SANFERNANDO064,Reach-1,6000
     498     816    1045     729    1393    2663    1908
River Rch & RM= SANFERNANDO064,Reach-1,3500
     713    1195    1569     941    2118    4766    2893
Boundary for River Rch & Prof#=SANFERNANDO064,Reach-1,1
Up Type=0
Dn Type=3
Dn Slope=0.005
Boundary for River Rch & Prof#=SANFERNANDO064,Reach-1,2
Up Type=0
Dn Type=3
Dn Slope=0.005
Boundary for River Rch & Prof#=SANFERNANDO064,Reach-1,3
Up Type=0
Dn Type=3
Dn Slope=0.005
Boundary for River Rch & Prof#=SANFERNANDO064,Reach-1,4
Up Type=0
Dn Type=3
Dn Slope=0.005
Boundary for River Rch & Prof#=SANFERNANDO064,Reach-1,5
Up Type=0
Dn Type=3
Dn Slope=0.005
Boundary for River Rch & Prof#=SANFERNANDO064,Reach-1,6
Up Type=0
Dn Type=3
Dn Slope=0.005
Boundary for River Rch & Prof#=SANFERNANDO064,Reach-1,7
Up Type=0
Dn Type=3
Dn Slope=0.005

--- SANFERNANDO064.g01 (geometry) ---

Geom Title=Existing Conditions

River Reach=SANFERNANDO064,Reach-1
Reach XY= 30
      2812102.50     10262451.00      2812693.25     10261974.00
      2812874.75     10261066.00      2812652.75     10260594.00
      2812639.00     10259690.00      2812351.50     10259436.00
      2812413.25     10259187.00      2812215.25     10258702.00
      2812450.75     10258441.00      2812441.75     10257979.00
      2812733.25     10257684.00      2812729.25     10257244.00
      2812408.25     10256835.00      2812310.00     10256413.00
      2811667.50     10256248.00      2811809.75     10255757.00
      2811591.25     10255547.00      2811110.25     10255532.00
      2810490.50     10254797.00      2810526.75     10254542.00
      2810749.25     10254371.00      2810715.50     10254221.00
      2810560.50     10254226.00      2810498.50     10253547.00
      2810160.50     10253419.00      2809406.50     10253735.00
      2809267.25     10253596.00      2809282.50     10253289.00
      2809675.00     10252912.00      2809561.00     10252677.00

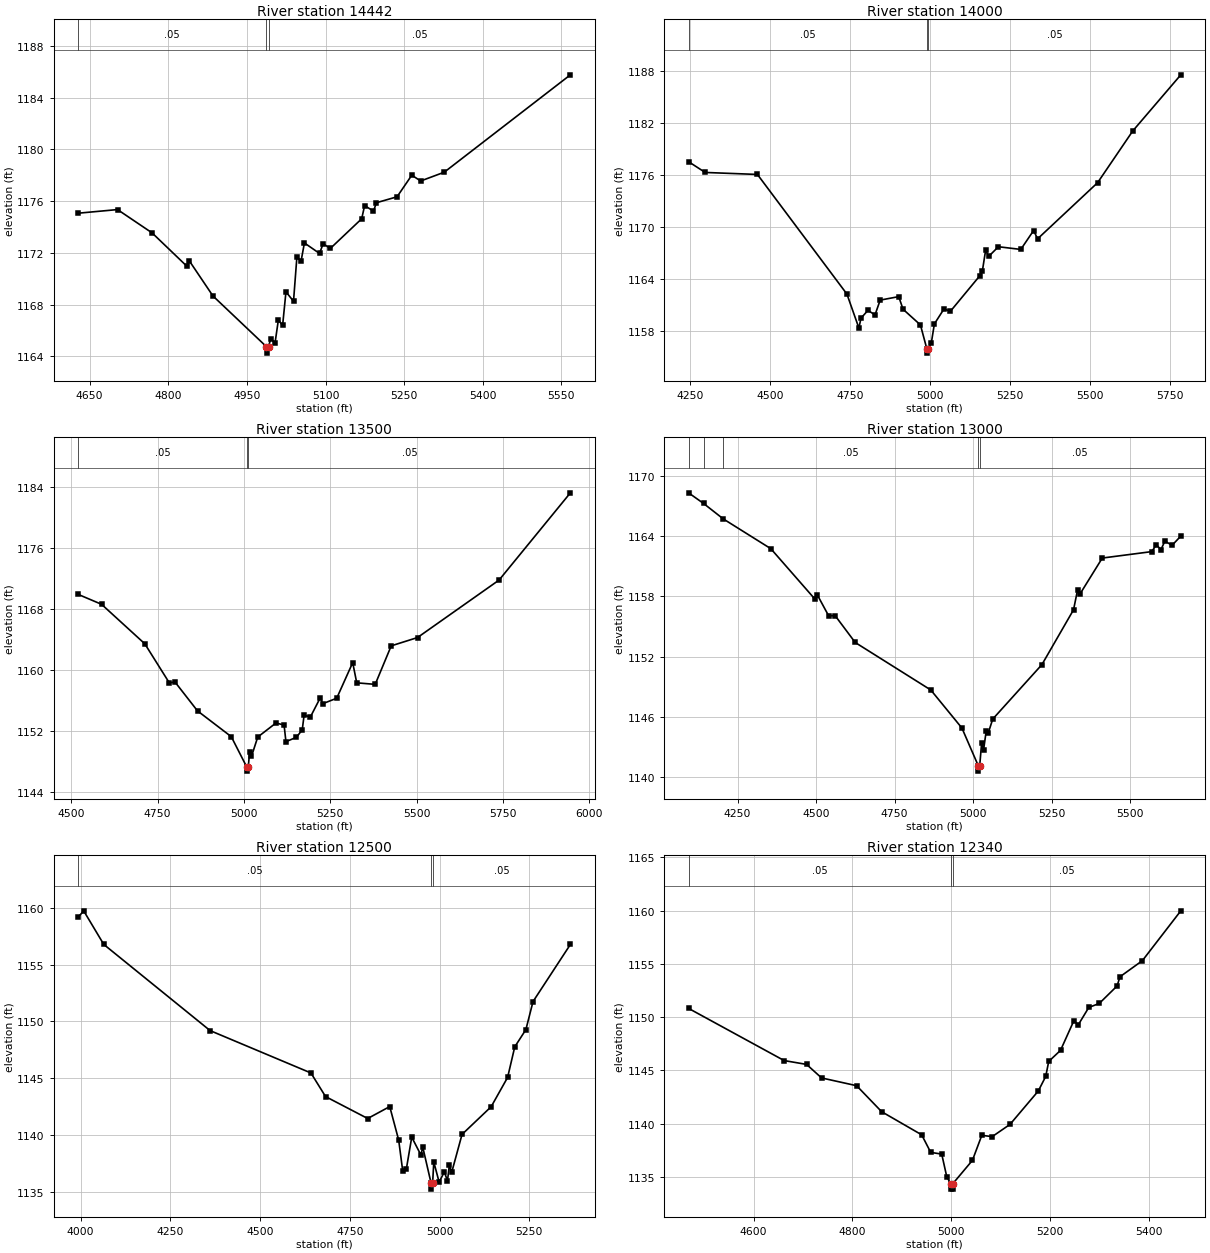
Type RM Length L Ch R = 1,14442,442,442,442
BEGIN DESCRIPTION:
Mapping XS aa45b752
END DESCRIPTION:
XS GIS Cut Line= 4
      2812371.25     10262723.86      2812296.74     10262477.25
      2812143.96     10262285.30      2811752.21     10262093.34
#Sta/Elev= 30
  4628.0 1175.06  4703.1 1175.34  4769.0 1173.54  4834.9 1170.98  4840.2 1171.37
  4885.2 1168.66  4987.2 1164.74  4987.5 1164.24  4991.2 1164.74  4995.6 1165.37
  5003.6 1165.01  5010.0 1166.80  5018.1 1166.38  5024.5 1168.98  5038.9 1168.25
  5045.3 1171.64  5053.3 1171.35  5059.7 1172.76  5088.5 1171.95  5095.4 1172.69
  5109.3 1172.34  5169.0 1174.63  5174.6 1175.65  5191.5 1175.22  5197.1 1175.87
  5236.5 1176.33  5264.6 1178.00  5281.5 1177.55  5326.5 1178.23  5567.2 1185.76
#Mann=3,-1,0
  4628.0    0.05       0  4987.2    0.05       0  4991.2    0.05       0
Bank Sta=4987.2,4991.2
Exp/Cntr=0.3,0.1

Type RM Length L Ch R = 1,14000,500,500,500
BEGIN DESCRIPTION:
SANFERNANDO064 28.0
END DESCRIPTION:
XS GIS Cut Line= 3
      2813205.69     10262453.11      2812539.56     10262096.66
      2811755.67     10262053.11
#Sta/Elev= 30
  4244.5 1177.52  4296.5 1176.28  4460.0 1176.05  4740.2 1162.26  4777.6 1158.35
  4784.1 1159.49  4806.0 1160.39  4828.0 1159.86  4844.2 1161.57  4902.3 1161.97
  4915.7 1160.52  4970.2 1158.71  4990.2 1155.96  4990.4 1155.46  4994.2 1155.96
  5004.4 1156.67  5013.9 1158.83  5043.9 1160.55  5064.0 1160.28  5156.6 1164.40
  5164.1 1164.94  5174.1 1167.29  5184.2 1166.62  5214.2 1167.72  5284.3 1167.41
  5324.4 1169.59  5336.9 1168.63  5524.7 1175.10  5634.9 1181.07  5785.1 1187.53
#Mann=3,-1,0
  4244.5    0.05       0  4990.2    0.05       0  4994.2    0.05       0
Bank Sta=4990.2,4994.2
Exp/Cntr=0.3,0.1

Type RM Length L Ch R = 1,13500,500,500,500
BEGIN DESCRIPTION:
SANFERNANDO064 27.0
END DESCRIPTION:
XS GIS Cut Line= 3
      2812955.68     10262103.11      2812725.34     10261681.54
      2811855.69     10262053.11
#Sta/Elev= 30
  4519.6 1169.90  4587.4 1168.60  4712.7 1163.42  4783.8 1158.29  4800.0 1158.42
  4865.4 1154.62  4963.2 1151.24  5008.5 1147.22  5008.7 1146.72  5012.5 1147.22
  5016.3 1149.28  5021.8 1148.66  5039.9 1151.19  5092.6 1153.03  5116.2 1152.77
  5121.6 1150.58  5151.9 1151.16  5168.8 1152.13  5174.2 1154.05  5192.4 1153.82
  5221.4 1156.37  5228.0 1155.56  5268.7 1156.28  5315.0 1160.95  5326.7 1158.30
  5380.2 1158.10  5426.6 1163.15  5502.8 1164.24  5739.1 1171.78  5945.7 1183.22
#Mann=3,-1,0
  4519.6    0.05       0  5008.5    0.05       0  5012.5    0.05       0
Bank Sta=5008.5,5012.5
Exp/Cntr=0.3,0.1

Type RM Length L Ch R = 1,13000,500,500,500
BEGIN DESCRIPTION:
SANFERNANDO064 26.0
END DESCRIPTION:
XS GIS Cut Line= 3
      2813455.69     10261853.12      2812828.67     10261199.29
      2812305.72     10261603.08
#Sta/Elev= 30
  4094.1 1168.28  4142.0 1167.22  4204.5 1165.69  4355.9 1162.73  4497.1 1157.69
  4504.4 1158.11  4539.6 1156.08  4561.0 1156.06  4624.5 1153.41  4865.1 1148.69
  4964.1 1144.91  5016.6 1141.13  5016.8 1140.63  5020.6 1141.13  5026.8 1143.43
  5033.1 1142.76  5041.3 1144.60  5047.6 1144.39  5062.1 1145.80  5218.6 1151.21
  5319.3 1156.66  5332.3 1158.65  5340.1 1158.24  5410.8 1161.80  5568.4 1162.44
  5582.9 1163.13  5597.4 1162.63  5610.2 1163.49  5632.7 1163.06  5660.7 1163.98
#Mann=5,-1,0
  4094.1    0.05       0  4142.0    0.12       0  4204.5    0.05       0
  5016.6    0.05       0  5020.6    0.05       0
Bank Sta=5016.6,5020.6
Exp/Cntr=0.3,0.1

Type RM Length L Ch R = 1,12500,160,160,160
BEGIN DESCRIPTION:
SANFERNANDO064 25.0
END DESCRIPTION:
XS GIS Cut Line= 3
      2813655.71     10261103.12      2812708.59     10260761.63
      2812355.65     10260853.12
#Sta/Elev= 30
  3993.2 1159.17  4008.6 1159.73  4064.6 1156.77  4360.9 1149.18  4641.7 1145.45
  4682.5 1143.37  4799.9 1141.44  4861.3 1142.49  4886.2 1139.54  4897.3 1136.86
  4907.4 1136.96  4922.6 1139.80  4948.0 1138.23  4953.3 1138.92  4976.7 1135.72
  4977.0 1135.22  4980.7 1135.72  4984.0 1137.61  4998.9 1135.84  5013.3 1136.73
  5022.2 1135.96  5027.3 1137.33  5034.0 1136.71  5062.7 1140.04  5143.9 1142.48
  5189.7 1145.06  5209.6 1147.75  5240.6 1149.27  5260.5 1151.74  5364.6 1156.77
#Mann=3,-1,0
  3993.2    0.05       0  4976.7    0.05       0  4980.7    0.05       0
Bank Sta=4976.7,4980.7
Exp/Cntr=0.3,0.1

Type RM Length L Ch R = 1,12340,340,340,340
BEGIN DESCRIPTION:
Mapping XS dca84dc7
END DESCRIPTION:
XS GIS Cut Line= 3
      2813181.41     10260700.47      2812617.15     10260604.98
      2812262.19     10260838.73
#Sta/Elev= 30
  4468.1 1150.82  4661.8 1145.92  4707.2 1145.56  4737.6 1144.29  4808.6 1143.56
  4859.3 1141.12  4940.4 1138.95  4958.7 1137.30  4981.0 1137.14  4991.2 1135.02
  4999.3 1134.35  4999.6 1133.85  5003.1 1133.85  5003.3 1134.35  5043.2 1136.55
  5062.2 1138.90  5083.3 1138.78  5119.4 1139.93  5176.6 1143.06  5191.7 1144.43
  5197.8 1145.84  5221.7 1146.88  5248.9 1149.68  5257.7 1149.28  5279.0 1150.91
  5300.1 1151.28  5336.2 1152.92  5342.2 1153.79  5387.5 1155.30  5465.4 1159.98
#Mann=3,-1,0
  4468.1    0.05       0  4999.3    0.05       0  5003.3    0.05       0
Bank Sta=4999.3,5003.3
Exp/Cntr=0.3,0.1

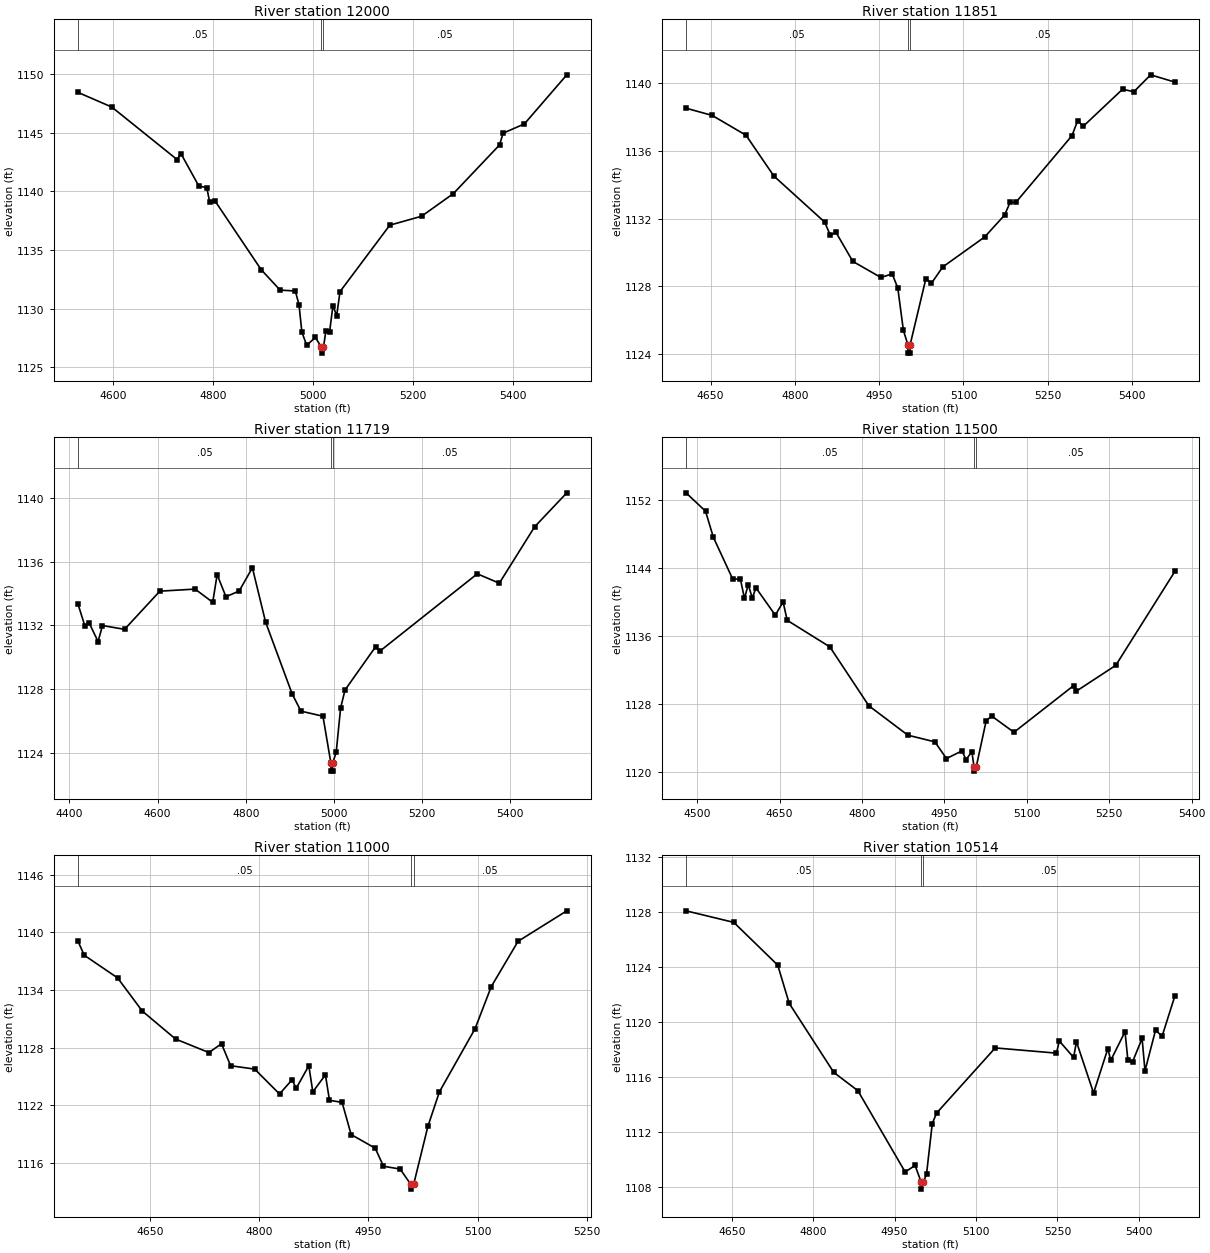
Type RM Length L Ch R = 1,12000,149,149,149
BEGIN DESCRIPTION:
SANFERNANDO064 24.0
END DESCRIPTION:
XS GIS Cut Line= 3
      2813055.70     10260503.12      2812644.87     10260275.46
      2812305.69     10260653.10
#Sta/Elev= 30
  4530.3 1148.45  4597.9 1147.20  4728.4 1142.72  4736.1 1143.23  4771.9 1140.46
  4787.9 1140.32  4793.6 1139.08  4803.9 1139.21  4896.6 1133.32  4934.4 1131.58
  4964.8 1131.50  4972.2 1130.34  4977.9 1127.99  4987.6 1126.87  5004.9 1127.54
  5017.1 1126.70  5017.4 1126.20  5021.1 1126.70  5025.8 1128.06  5033.3 1127.99
  5040.0 1130.25  5047.5 1129.39  5054.2 1131.45  5153.7 1137.12  5217.2 1137.88
  5280.7 1139.81  5373.2 1143.97  5380.2 1144.97  5422.8 1145.76  5507.6 1149.95
#Mann=3,-1,0
  4530.3    0.05       0  5017.1    0.05       0  5021.1    0.05       0
Bank Sta=5017.1,5021.1
Exp/Cntr=0.3,0.1

Type RM Length L Ch R = 1,11851,132,132,132
BEGIN DESCRIPTION:
Mapping XS 427f6f65
END DESCRIPTION:
XS GIS Cut Line= 2
      2813072.41     10260142.46      2812202.72     10260118.96
#Sta/Elev= 30
  4606.2 1138.52  4652.9 1138.09  4713.0 1136.92  4762.6 1134.51  4853.0 1131.79
  4863.0 1131.01  4873.0 1131.19  4903.0 1129.47  4953.0 1128.52  4973.1 1128.73
  4983.1 1127.90  4993.1 1125.39  5001.1 1124.55  5001.3 1124.05  5004.8 1124.05
  5005.1 1124.55  5033.1 1128.45  5043.1 1128.18  5063.1 1129.14  5137.7 1130.91
  5173.1 1132.20  5183.1 1132.96  5193.1 1132.95  5293.2 1136.90  5303.2 1137.78
  5313.2 1137.45  5383.2 1139.64  5403.2 1139.49  5433.2 1140.49  5476.2 1140.06
#Mann=3,-1,0
  4606.2    0.05       0  5001.1    0.05       0  5005.1    0.05       0
Bank Sta=5001.1,5005.1
Exp/Cntr=0.3,0.1

Type RM Length L Ch R = 1,11719,219,219,219
BEGIN DESCRIPTION:
Mapping XS 4d6a7e9e
END DESCRIPTION:
XS GIS Cut Line= 2
      2813221.29     10260024.94      2812112.63     10259997.52
#Sta/Elev= 30
  4419.4 1133.33  4435.0 1131.96  4445.0 1132.13  4465.0 1130.97  4475.0 1131.98
  4525.0 1131.74  4605.1 1134.14  4685.1 1134.27  4725.1 1133.44  4735.1 1135.18
  4755.1 1133.79  4785.1 1134.15  4815.1 1135.61  4845.1 1132.19  4905.2 1127.69
  4925.2 1126.60  4975.2 1126.28  4993.2 1123.33  4993.4 1122.83  4996.9 1122.83
  4997.2 1123.33  5005.2 1124.01  5015.2 1126.79  5025.2 1127.93  5095.0 1130.66
  5105.2 1130.39  5325.3 1135.23  5375.3 1134.64  5455.3 1138.18  5528.4 1140.32
#Mann=3,-1,0
  4419.4    0.05       0  4993.2    0.05       0  4997.2    0.05       0
Bank Sta=4993.2,4997.2
Exp/Cntr=0.3,0.1

Type RM Length L Ch R = 1,11500,500,500,500
BEGIN DESCRIPTION:
SANFERNANDO064 23.0
END DESCRIPTION:
XS GIS Cut Line= 3
      2813005.69     10259453.11      2812621.53     10259804.01
      2812255.66     10259753.11
#Sta/Elev= 30
  4479.7 1152.85  4515.2 1150.69  4529.4 1147.63  4564.5 1142.73  4578.7 1142.69
  4586.1 1140.43  4592.9 1142.06  4600.3 1140.48  4607.1 1141.67  4642.2 1138.46
  4656.4 1140.02  4663.8 1137.86  4741.5 1134.73  4812.4 1127.81  4883.4 1124.35
  4932.7 1123.56  4953.7 1121.60  4982.0 1122.50  4989.4 1121.47  5000.0 1122.42
  5003.9 1120.62  5004.2 1120.12  5007.9 1120.62  5026.1 1126.06  5036.2 1126.59
  5076.6 1124.69  5185.3 1130.18  5190.3 1129.53  5261.9 1132.56  5369.4 1143.60
#Mann=3,-1,0
  4479.7    0.05       0  5003.9    0.05       0  5007.9    0.05       0
Bank Sta=5003.9,5007.9
Exp/Cntr=0.3,0.1

Type RM Length L Ch R = 1,11000,486,486,486
BEGIN DESCRIPTION:
SANFERNANDO064 22.0
END DESCRIPTION:
XS GIS Cut Line= 3
      2812805.66     10259303.13      2812398.86     10259492.70
      2812205.69     10259603.11
#Sta/Elev= 30
  4551.2 1139.07  4559.8 1137.61  4605.6 1135.25  4639.5 1131.80  4685.2 1128.89
  4731.0 1127.48  4748.3 1128.40  4760.8 1126.11  4793.9 1125.76  4828.0 1123.17
  4845.3 1124.66  4850.8 1123.75  4868.2 1126.11  4873.7 1123.39  4891.0 1125.16
  4896.6 1122.51  4913.9 1122.30  4926.3 1118.95  4959.4 1117.53  4970.7 1115.65
  4993.6 1115.36  5008.2 1113.77  5008.4 1113.27  5012.2 1113.77  5031.8 1119.82
  5047.6 1123.40  5096.5 1129.96  5118.8 1134.35  5155.6 1139.06  5222.5 1142.23
#Mann=3,-1,0
  4551.2    0.05       0  5008.2    0.05       0  5012.2    0.05       0
Bank Sta=5008.2,5012.2
Exp/Cntr=0.3,0.1

Type RM Length L Ch R = 1,10514,514,514,514
BEGIN DESCRIPTION:
Mapping XS 9119248f
END DESCRIPTION:
XS GIS Cut Line= 2
      2812715.90     10258990.73      2811861.91     10259276.70
#Sta/Elev= 30
  4565.8 1128.07  4653.8 1127.23  4734.8 1124.12  4755.9 1121.34  4838.0 1116.32
  4882.4 1114.99  4969.5 1109.08  4987.9 1109.55  4999.1 1108.33  4999.3 1107.83
  5003.1 1108.33  5009.0 1108.95  5019.5 1112.60  5027.4 1113.36  5135.5 1118.10
  5248.3 1117.72  5253.6 1118.60  5279.9 1117.41  5285.1 1118.55  5316.7 1114.82
  5343.0 1118.05  5348.3 1117.19  5374.6 1119.28  5379.8 1117.25  5388.6 1117.10
  5406.1 1118.79  5411.4 1116.43  5430.8 1119.38  5443.0 1118.96  5466.4 1121.87
#Mann=3,-1,0
  4565.8    0.05       0  4999.1    0.05       0  5003.1    0.05       0
Bank Sta=4999.1,5003.1
Exp/Cntr=0.3,0.1

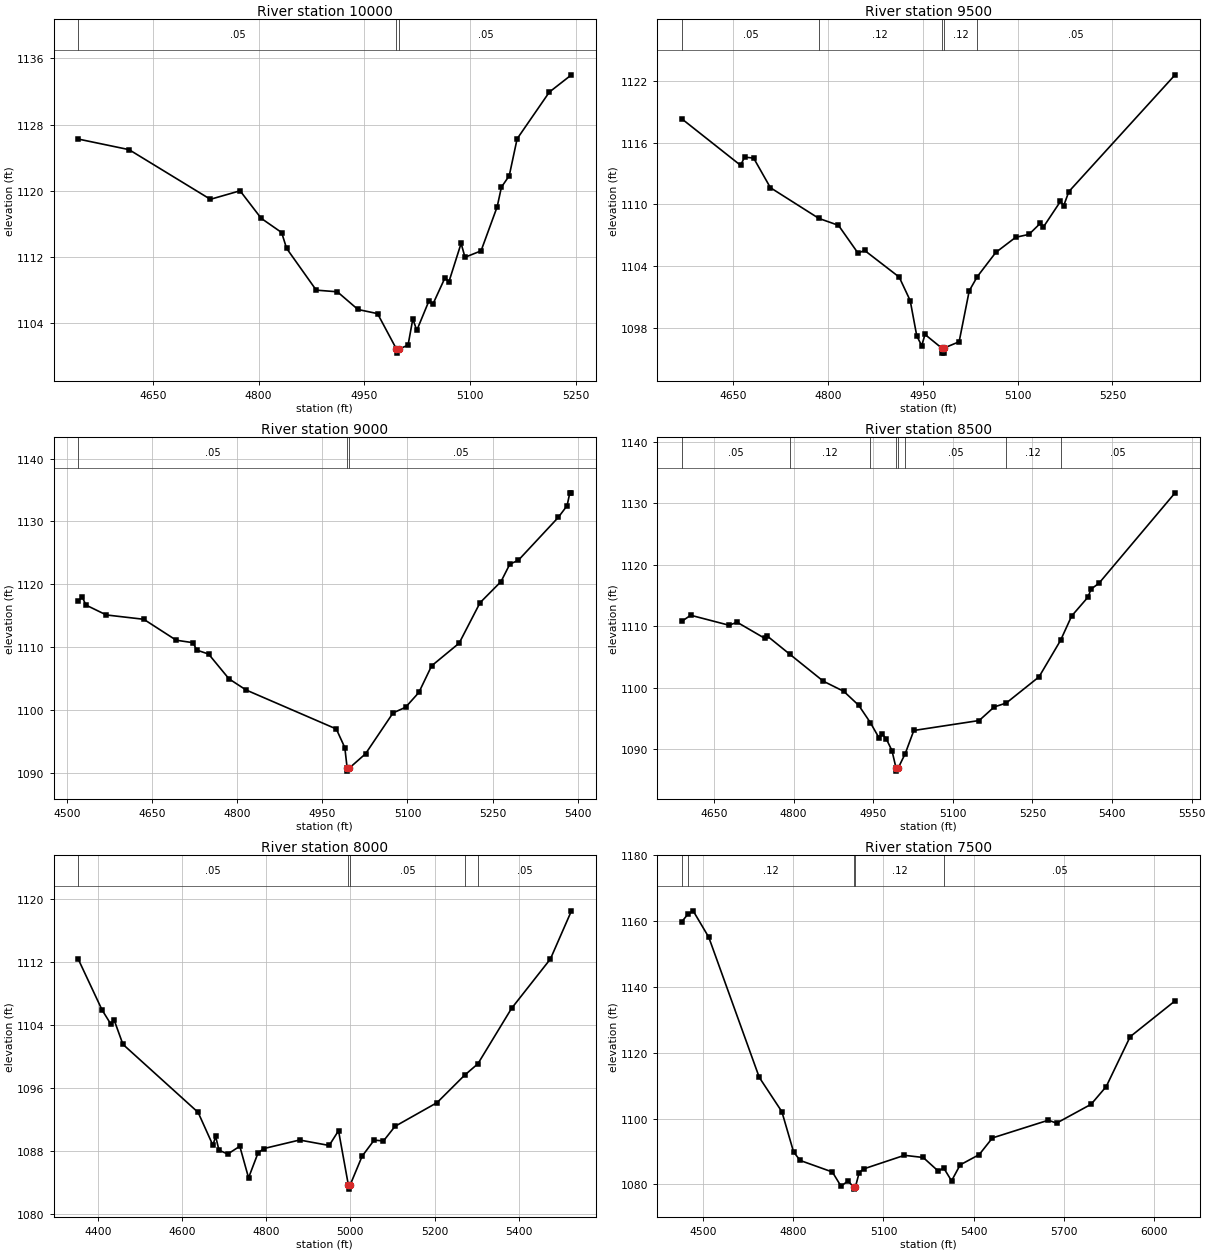
Type RM Length L Ch R = 1,10000,500,500,500
BEGIN DESCRIPTION:
SANFERNANDO064 20.0
END DESCRIPTION:
XS GIS Cut Line= 3
      2812605.65     10258903.09      2812226.65     10258649.53
      2812005.72     10258753.09
#Sta/Elev= 30
  4544.0 1126.25  4616.1 1124.97  4731.6 1118.96  4773.7 1119.99  4803.7 1116.66
  4832.7 1114.94  4839.7 1113.03  4881.8 1107.97  4911.8 1107.77  4941.0 1105.63
  4968.8 1105.13  4995.6 1100.85  4995.8 1100.35  4999.6 1100.85  5012.1 1101.32
  5018.9 1104.49  5024.5 1103.10  5041.8 1106.68  5047.3 1106.26  5064.6 1109.48
  5070.1 1108.98  5087.4 1113.63  5092.9 1111.95  5115.7 1112.72  5138.6 1118.06
  5144.6 1120.43  5155.7 1121.81  5166.9 1126.28  5212.6 1131.93  5244.0 1134.02
#Mann=3,-1,0
  4544.0    0.05       0  4995.6    0.05       0  4999.6    0.05       0
Bank Sta=4995.6,4999.6
Exp/Cntr=0.3,0.1

Type RM Length L Ch R = 1,9500,500,500,500
BEGIN DESCRIPTION:
SANFERNANDO064 19.0
END DESCRIPTION:
XS GIS Cut Line= 3
      2812805.69     10258453.11      2812387.93     10258345.91
      2812055.70     10258453.11
#Sta/Elev= 30
  4568.7 1118.30  4661.6 1113.80  4668.0 1114.59  4682.3 1114.50  4708.8 1111.63
  4785.5 1108.65  4816.5 1107.98  4847.5 1105.28  4857.8 1105.55  4912.6 1102.96
  4930.0 1100.68  4940.4 1097.26  4948.2 1096.31  4953.4 1097.40  4979.7 1096.09
  4979.9 1095.59  4983.4 1095.59  4983.7 1096.09  5007.4 1096.69  5023.4 1101.63
  5036.2 1103.01  5065.4 1105.35  5096.9 1106.82  5117.9 1107.10  5135.6 1108.16
  5140.8 1107.82  5167.6 1110.29  5172.9 1109.89  5181.0 1111.25  5349.1 1122.57
#Mann=5,-1,0
  4568.7    0.05       0  4785.5    0.12       0  4979.7    0.07       0
  4983.7    0.12       0  5036.2    0.05       0
Bank Sta=4979.7,4983.7
Exp/Cntr=0.3,0.1

Type RM Length L Ch R = 1,9000,500,500,500
BEGIN DESCRIPTION:
SANFERNANDO064 18.0
END DESCRIPTION:
XS GIS Cut Line= 3
      2812805.67     10258303.09      2812538.31     10257904.45
      2812205.70     10257703.12
#Sta/Elev= 30
  4520.0 1117.40  4527.5 1117.90  4533.5 1116.69  4569.5 1115.11  4635.5 1114.42
  4692.6 1111.09  4722.5 1110.69  4728.6 1109.52  4749.6 1108.89  4785.6 1104.94
  4815.6 1103.17  4974.6 1096.96  4989.6 1093.99  4993.7 1090.75  4993.9 1090.25
  4997.7 1090.75  5026.1 1093.01  5074.6 1099.52  5096.6 1100.41  5120.0 1102.77
  5142.5 1107.01  5191.0 1110.62  5227.8 1117.06  5264.7 1120.42  5280.2 1123.19
  5295.3 1123.82  5365.6 1130.64  5381.1 1132.50  5385.9 1134.55  5388.8 1134.55
#Mann=3,-1,0
  4520.0    0.05       0  4993.7    0.05       0  4997.7    0.05       0
Bank Sta=4993.7,4997.7
Exp/Cntr=0.3,0.1

Type RM Length L Ch R = 1,8500,500,500,500
BEGIN DESCRIPTION:
SANFERNANDO064 17.0
END DESCRIPTION:
XS GIS Cut Line= 3
      2813105.66     10257603.10      2812711.53     10257487.98
      2812205.67     10257603.11
#Sta/Elev= 30
  4589.4 1110.81  4606.1 1111.79  4678.2 1110.17  4693.6 1110.65  4745.2 1108.06
  4750.4 1108.41  4792.8 1105.45  4855.9 1101.07  4894.6 1099.41  4922.7 1097.14
  4944.6 1094.33  4961.5 1091.76  4966.7 1092.49  4974.8 1091.65  4985.3 1089.78
  4993.0 1086.94  4993.2 1086.44  4997.0 1086.94  5010.3 1089.28  5026.5 1093.05
  5149.6 1094.67  5178.0 1096.88  5200.6 1097.51  5262.4 1101.77  5302.9 1107.69
  5323.9 1111.67  5354.7 1114.74  5360.4 1116.04  5375.2 1116.98  5518.8 1131.70
#Mann=8,-1,0
  4589.4    0.05       0  4792.8    0.12       0  4944.6    0.05       0
  4993.0    0.07       0  4997.0    0.05       0  5010.3    0.05       0
  5200.6    0.12       0  5302.9    0.05       0
Bank Sta=4993,4997
Exp/Cntr=0.3,0.1

Type RM Length L Ch R = 1,8000,500,500,500
BEGIN DESCRIPTION:
SANFERNANDO064 16.0
END DESCRIPTION:
XS GIS Cut Line= 3
      2813005.67     10256553.13      2812594.87     10257052.21
      2812255.71     10257453.09
#Sta/Elev= 30
  4353.6 1112.33  4410.2 1105.89  4431.3 1104.07  4438.9 1104.62  4459.8 1101.53
  4638.4 1092.91  4673.5 1088.75  4680.0 1089.87  4687.9 1088.13  4708.7 1087.63
  4737.4 1088.62  4758.2 1084.62  4780.4 1087.73  4793.9 1088.32  4879.4 1089.41
  4949.7 1088.72  4971.9 1090.59  4995.3 1083.69  4995.6 1083.19  4999.3 1083.69
  5027.9 1087.36  5056.5 1089.40  5078.6 1089.29  5106.0 1091.14  5206.0 1094.15
  5271.3 1097.62  5302.8 1099.06  5382.8 1106.08  5475.1 1112.34  5525.1 1118.44
#Mann=5,-1,0
  4353.6    0.05       0  4995.3    0.05       0  4999.3    0.05       0
  5271.3    0.12       0  5302.8    0.05       0
Bank Sta=4995.3,4999.3
Exp/Cntr=0.3,0.1

Type RM Length L Ch R = 1,7500,500,500,500
BEGIN DESCRIPTION:
SANFERNANDO064 15.0
END DESCRIPTION:
XS GIS Cut Line= 3
      2812605.69     10256103.09      2812373.53     10256625.31
      2811505.70     10257253.10
#Sta/Elev= 30
  4428.5 1159.84  4448.0 1162.02  4466.1 1163.12  4518.1 1155.11  4686.3 1112.54
  4761.6 1102.11  4800.6 1089.89  4822.5 1087.30  4929.8 1083.79  4958.5 1079.49
  4981.8 1081.06  5002.1 1079.09  5002.4 1078.59  5006.1 1079.09  5018.9 1083.56
  5033.6 1084.72  5169.7 1088.86  5232.3 1088.20  5282.6 1084.05  5300.4 1085.03
  5326.7 1081.10  5355.3 1085.95  5418.7 1089.07  5462.8 1094.14  5649.2 1099.53
  5676.3 1098.63  5791.5 1104.37  5841.8 1109.75  5921.5 1124.89  6071.1 1135.78
#Mann=5,-1,0
  4428.5    0.05       0  4448.0    0.12       0  5002.1    0.07       0
  5006.1    0.12       0  5300.4    0.05       0
Bank Sta=5002.1,5006.1
Exp/Cntr=0.3,0.1

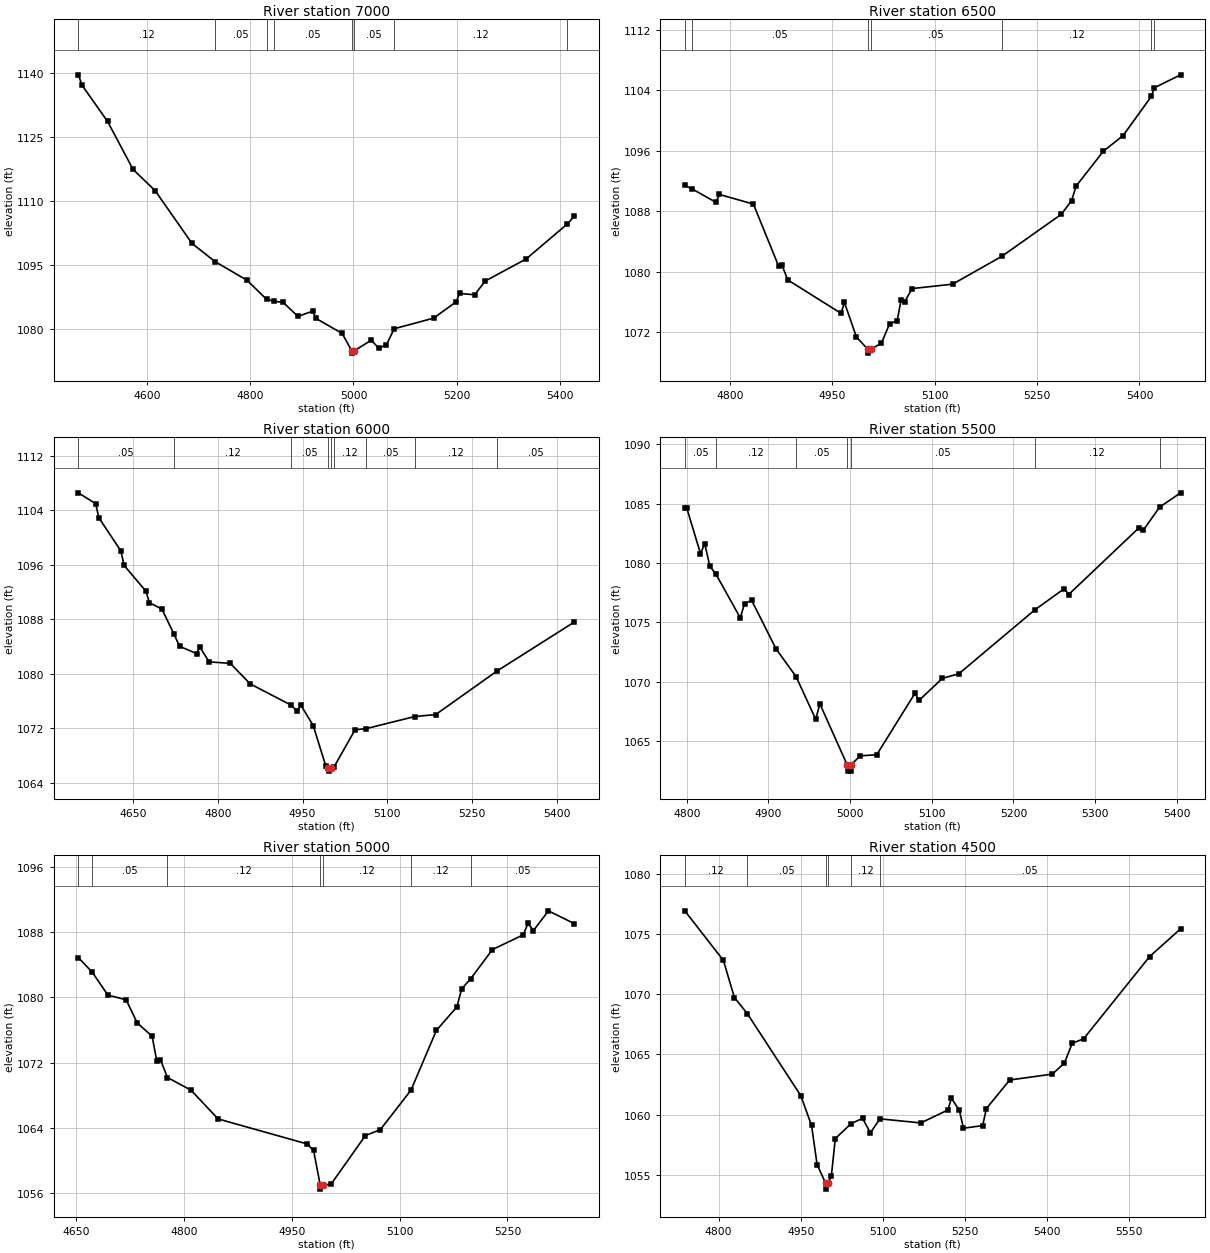
Type RM Length L Ch R = 1,7000,500,500,500
BEGIN DESCRIPTION:
SANFERNANDO064 14.0
END DESCRIPTION:
XS GIS Cut Line= 3
      2812455.69     10256053.11      2812049.00     10256398.10
      2811705.66     10256653.13
#Sta/Elev= 30
  4466.7 1139.60  4473.8 1137.18  4523.3 1128.68  4572.7 1117.43  4615.5 1112.44
  4687.0 1100.05  4732.0 1095.76  4793.5 1091.42  4831.5 1086.95  4845.6 1086.50
  4863.8 1086.22  4892.3 1082.93  4920.9 1084.16  4927.5 1082.45  4978.1 1078.93
  4996.9 1074.82  4997.1 1074.32  5000.9 1074.82  5034.4 1077.35  5049.0 1075.49
  5063.6 1076.24  5079.0 1080.04  5155.4 1082.53  5199.2 1086.38  5205.5 1088.32
  5234.7 1088.01  5255.5 1091.24  5334.8 1096.42  5414.3 1104.60  5427.7 1106.39
#Mann=8,-1,0
  4466.7    0.12       0  4732.0    0.05       0  4831.5    0.12       0
  4845.6    0.05       0  4996.9    0.05       0  5000.9    0.05       0
  5079.0    0.12       0  5414.3    0.05       0
Bank Sta=4996.9,5000.9
Exp/Cntr=0.3,0.1

Type RM Length L Ch R = 1,6500,500,500,500
BEGIN DESCRIPTION:
SANFERNANDO064 13.0
END DESCRIPTION:
XS GIS Cut Line= 3
      2811905.64     10256153.12      2811641.30     10256181.85
      2811455.70     10256603.08
#Sta/Elev= 30
  4734.1 1091.42  4744.2 1091.00  4779.8 1089.19  4784.9 1090.23  4834.6 1088.96
  4871.4 1080.79  4876.4 1080.90  4884.9 1078.94  4962.9 1074.53  4967.9 1075.96
  4985.5 1071.40  5002.2 1069.77  5002.4 1069.27  5006.2 1069.77  5022.0 1070.57
  5034.2 1073.18  5045.1 1073.52  5050.8 1076.28  5056.3 1076.07  5066.9 1077.80
  5126.3 1078.38  5198.1 1082.04  5285.5 1087.61  5300.5 1089.40  5307.3 1091.35
  5347.2 1095.95  5376.0 1098.01  5417.4 1103.19  5421.9 1104.34  5460.3 1106.04
#Mann=7,-1,0
  4734.1    0.12       0  4744.2    0.05       0  5002.2    0.05       0
  5006.2    0.05       0  5198.1    0.12       0  5417.4    0.05       0
  5421.9    0.12       0
Bank Sta=5002.2,5006.2
Exp/Cntr=0.3,0.1

Type RM Length L Ch R = 1,6000,500,500,500
BEGIN DESCRIPTION:
SANFERNANDO064 12.0
END DESCRIPTION:
XS GIS Cut Line= 3
      2812205.72     10255553.09      2811806.80     10255754.09
      2811455.65     10256003.14
#Sta/Elev= 30
  4553.3 1106.53  4584.0 1104.94  4589.6 1102.88  4628.6 1098.01  4634.2 1095.90
  4673.2 1092.08  4678.8 1090.43  4701.2 1089.49  4722.8 1085.77  4732.5 1084.03
  4762.5 1082.97  4768.1 1083.93  4784.8 1081.75  4822.1 1081.54  4857.3 1078.53
  4929.3 1075.43  4941.0 1074.50  4946.6 1075.47  4968.9 1072.41  4991.2 1066.46
  4995.8 1066.24  4996.1 1065.74  4999.8 1066.24  5005.2 1066.29  5042.9 1071.80
  5062.1 1071.96  5148.4 1073.74  5185.6 1074.03  5293.8 1080.40  5430.5 1087.58
#Mann=9,-1,0
  4553.3    0.05       0  4722.8    0.12       0  4929.3    0.05       0
  4995.8    0.05       0  4999.8    0.05       0  5005.2    0.12       0
  5062.1    0.05       0  5148.4    0.12       0  5293.8    0.05       0
Bank Sta=4995.8,4999.8
Exp/Cntr=0.3,0.1

Type RM Length L Ch R = 1,5500,500,500,500
BEGIN DESCRIPTION:
SANFERNANDO064 11.0
END DESCRIPTION:
XS GIS Cut Line= 3
      2811355.69     10255353.13      2811399.44     10255550.74
      2811355.69     10255953.07
#Sta/Elev= 30
  4797.6 1084.61  4800.1 1084.61  4816.8 1080.79  4822.0 1081.61  4828.3 1079.72
  4835.7 1079.06  4865.6 1075.36  4870.7 1076.58  4879.5 1076.84  4909.2 1072.77
  4933.9 1070.41  4957.9 1066.82  4963.0 1068.12  4996.6 1062.95  4996.9 1062.45
  5000.5 1062.45  5000.7 1062.95  5012.4 1063.74  5032.6 1063.83  5079.4 1069.01
  5084.4 1068.41  5113.0 1070.27  5133.2 1070.66  5226.1 1076.04  5262.4 1077.84
  5267.5 1077.33  5354.0 1082.98  5359.0 1082.76  5378.9 1084.70  5404.7 1085.91
#Mann=7,-1,0
  4797.6    0.05       0  4835.7    0.12       0  4933.9    0.05       0
  4996.6    0.05       0  5000.7    0.05       0  5226.1    0.12       0
  5378.9    0.05       0
Bank Sta=4996.6,5000.7
Exp/Cntr=0.3,0.1

Type RM Length L Ch R = 1,5000,500,500,500
BEGIN DESCRIPTION:
SANFERNANDO064 10.0
END DESCRIPTION:
XS GIS Cut Line= 3
      2811055.69     10255053.09      2810977.13     10255391.50
      2810755.66     10255653.15
#Sta/Elev= 30
  4652.6 1084.85  4672.1 1083.05  4693.7 1080.26  4719.1 1079.68  4734.7 1076.84
  4755.3 1075.22  4761.8 1072.19  4766.9 1072.34  4776.7 1070.16  4809.6 1068.60
  4847.1 1065.09  4970.9 1062.03  4980.1 1061.23  4989.3 1056.99  4989.6 1056.49
  4993.4 1056.99  5004.3 1057.08  5052.2 1063.05  5073.0 1063.78  5115.6 1068.60
  5151.0 1075.93  5179.6 1078.82  5186.2 1081.02  5198.8 1082.27  5229.0 1085.83
  5271.9 1087.64  5278.5 1089.03  5286.2 1088.17  5307.0 1090.58  5342.8 1089.02
#Mann=7,-1,0
  4652.6    0.12       0  4672.1    0.05       0  4776.7    0.12       0
  4989.3    0.05       0  4993.4    0.12       0  5115.6    0.12       0
  5198.8    0.05       0
Bank Sta=4989.3,4993.4
Exp/Cntr=0.3,0.1

Type RM Length L Ch R = 1,4500,500,500,500
BEGIN DESCRIPTION:
SANFERNANDO064 9.0
END DESCRIPTION:
XS GIS Cut Line= 3
      2810955.71     10254953.11      2810695.72     10254984.69
      2810205.66     10255403.13
#Sta/Elev= 30
  4738.1 1076.91  4808.6 1072.80  4828.8 1069.72  4852.6 1068.37  4950.1 1061.58
  4969.8 1059.11  4979.9 1055.87  4995.4 1054.33  4995.7 1053.83  4999.6 1054.33
  5005.9 1054.89  5013.2 1058.02  5042.2 1059.27  5063.0 1059.70  5077.3 1058.50
  5094.8 1059.66  5169.5 1059.32  5218.9 1060.39  5225.5 1061.36  5239.8 1060.38
  5247.5 1058.88  5282.6 1059.10  5289.3 1060.51  5332.0 1062.88  5410.0 1063.37
  5431.9 1064.28  5446.2 1065.92  5467.1 1066.30  5587.8 1073.12  5644.4 1075.42
#Mann=6,-1,0
  4738.1    0.12       0  4852.6    0.05       0  4995.4    0.05       0
  4999.6    0.05       0  5042.2    0.12       0  5094.8    0.05       0
Bank Sta=4995.4,4999.6
Exp/Cntr=0.3,0.1

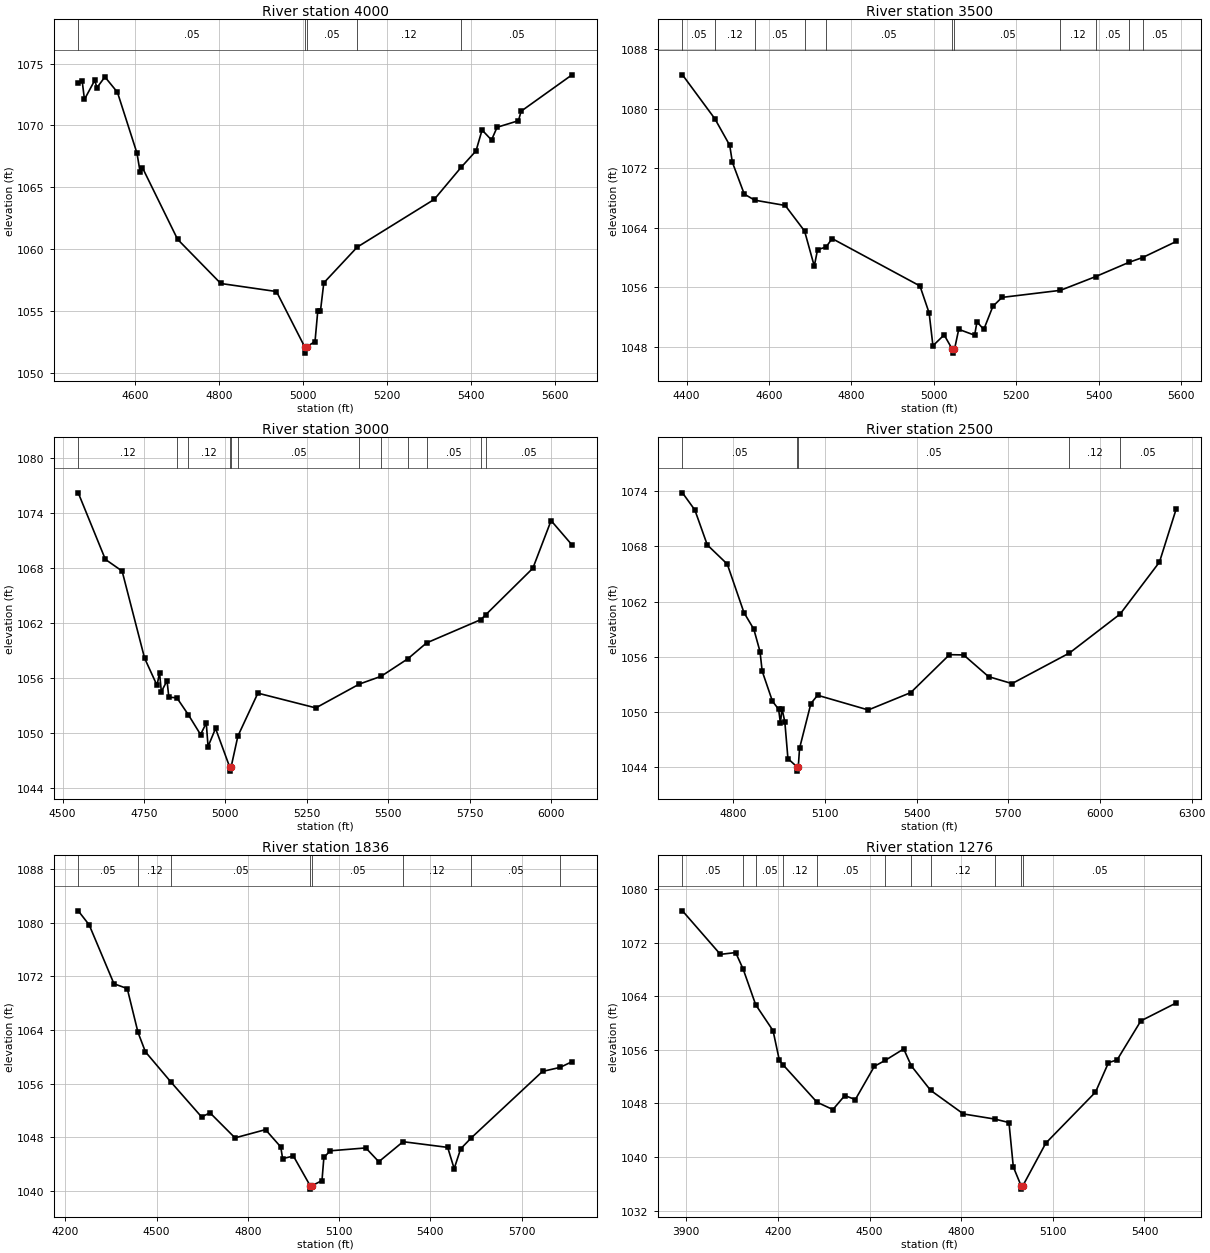
Type RM Length L Ch R = 1,4000,500,500,500
BEGIN DESCRIPTION:
SANFERNANDO064 8.0
END DESCRIPTION:
XS GIS Cut Line= 3
      2811005.65     10254803.10      2810508.04     10254606.32
      2810005.65     10255003.14
#Sta/Elev= 30
  4464.9 1073.39  4474.3 1073.59  4479.7 1072.10  4504.1 1073.64  4509.5 1073.05
  4528.4 1073.92  4558.2 1072.68  4604.7 1067.76  4612.2 1066.23  4617.6 1066.59
  4701.4 1060.79  4804.2 1057.22  4936.7 1056.57  5004.0 1052.09  5004.3 1051.59
  5008.3 1052.09  5028.5 1052.53  5035.0 1054.98  5041.4 1054.99  5049.4 1057.27
  5128.9 1060.16  5312.3 1064.02  5376.2 1066.61  5411.7 1067.94  5426.1 1069.63
  5448.6 1068.82  5461.8 1069.85  5512.7 1070.38  5519.1 1071.15  5640.2 1074.09
#Mann=5,-1,0
  4464.9    0.05       0  5004.0    0.05       0  5008.3    0.05       0
  5128.9    0.12       0  5376.2    0.05       0
Bank Sta=5004,5008.3
Exp/Cntr=0.3,0.1

Type RM Length L Ch R = 1,3500,500,500,500
BEGIN DESCRIPTION:
SANFERNANDO064 7.0
END DESCRIPTION:
XS GIS Cut Line= 3
      2811105.71     10253753.08      2810727.79     10254232.17
      2810205.70     10254503.10
#Sta/Elev= 30
  4389.8 1084.56  4468.5 1078.65  4504.5 1075.09  4510.9 1072.81  4539.8 1068.53
  4565.2 1067.71  4639.2 1067.00  4686.2 1063.56  4709.7 1058.85  4717.7 1061.05
  4738.5 1061.42  4753.0 1062.55  4966.2 1056.18  4988.5 1052.54  4997.7 1048.14
  5024.9 1049.60  5044.9 1047.65  5045.2 1047.15  5050.0 1047.65  5060.3 1050.35
  5098.9 1049.56  5104.6 1051.36  5121.1 1050.33  5143.2 1053.44  5165.3 1054.64
  5307.1 1055.59  5392.7 1057.44  5474.2 1059.37  5506.6 1060.00  5588.2 1062.16
#Mann=11,-1,0
  4389.8    0.05       0  4468.5    0.12       0  4565.2    0.05       0
  4686.2    0.12       0  4738.5    0.05       0  5044.9    0.03       0
  5050.0    0.05       0  5307.1    0.12       0  5392.7    0.05       0
  5474.2    0.12       0  5506.6    0.05       0
Bank Sta=5044.9,5050
Exp/Cntr=0.3,0.1

Type RM Length L Ch R = 1,3000,500,500,500
BEGIN DESCRIPTION:
SANFERNANDO064 6.0
END DESCRIPTION:
XS GIS Cut Line= 3
      2811005.67     10253753.12      2810594.66     10253941.42
      2809905.67     10254753.13
#Sta/Elev= 30
  4547.9 1076.23  4631.2 1068.97  4682.7 1067.69  4751.7 1058.19  4789.9 1055.22
  4797.7 1056.60  4803.2 1054.52  4820.7 1055.73  4826.2 1053.93  4850.9 1053.86
  4886.4 1052.00  4923.7 1049.85  4941.2 1051.11  4946.7 1048.54  4969.7 1050.52
  5012.6 1046.36  5013.0 1045.86  5017.8 1046.36  5038.4 1049.69  5099.7 1054.37
  5277.7 1052.76  5411.4 1055.36  5478.4 1056.21  5560.4 1058.12  5617.9 1059.85
  5784.4 1062.39  5800.1 1062.94  5944.4 1068.00  6000.4 1073.20  6064.7 1070.54
#Mann=12,-1,0
  4547.9    0.12       0  4850.9    0.05       0  4886.4    0.12       0
  5012.6    0.07       0  5017.8    0.12       0  5038.4    0.05       0
  5411.4    0.12       0  5478.4    0.05       0  5560.4    0.12       0
  5617.9    0.05       0  5784.4    0.12       0  5800.1    0.05       0
Bank Sta=5012.6,5017.8
Exp/Cntr=0.3,0.1

Type RM Length L Ch R = 1,2500,664,664,664
BEGIN DESCRIPTION:
SANFERNANDO064 5.0
END DESCRIPTION:
XS GIS Cut Line= 3
      2810355.69     10253153.13      2810418.31     10253513.53
      2809905.67     10254653.14
#Sta/Elev= 30
  4634.2 1073.84  4674.8 1071.97  4715.4 1068.17  4780.8 1066.08  4835.4 1060.80
  4867.6 1059.00  4887.9 1056.56  4895.0 1054.43  4928.5 1051.16  4948.8 1050.27
  4954.7 1048.76  4959.8 1050.35  4969.1 1048.91  4979.3 1044.90  5007.8 1044.04
  5008.2 1043.54  5013.2 1044.04  5017.3 1046.03  5054.4 1050.90  5076.3 1051.80
  5242.1 1050.20  5381.0 1052.09  5507.8 1056.22  5554.1 1056.19  5635.5 1053.83
  5712.3 1053.07  5900.2 1056.40  6066.0 1060.64  6194.7 1066.30  6249.6 1072.10
#Mann=5,-1,0
  4634.2    0.05       0  5007.8    0.03       0  5013.2    0.05       0
  5900.2    0.12       0  6066.0    0.05       0
Bank Sta=5007.8,5013.2
Exp/Cntr=0.3,0.1

Type RM Length L Ch R = 1,1836,560,560,560
BEGIN DESCRIPTION:
Mapping XS 82712ffb
END DESCRIPTION:
XS GIS Cut Line= 4
      2810277.73     10252995.99      2810034.67     10253438.72
      2809765.57     10253638.37      2809357.59     10254306.76
#Sta/Elev= 30
  4242.3 1081.79  4278.3 1079.69  4359.8 1070.90  4403.4 1070.19  4438.7 1063.66
  4463.1 1060.75  4548.1 1056.18  4647.9 1051.02  4675.4 1051.64  4757.7 1047.90
  4857.9 1049.13  4908.0 1046.55  4914.2 1044.80  4949.6 1045.19  5004.8 1040.75
  5005.3 1040.25  5010.3 1040.75  5043.6 1041.53  5049.8 1044.98  5070.6 1045.97
  5187.7 1046.40  5230.3 1044.34  5310.2 1047.33  5456.8 1046.48  5478.1 1043.30
  5499.4 1046.26  5534.5 1047.91  5768.5 1057.82  5826.3 1058.42  5865.5 1059.27
#Mann=8,-1,0
  4242.3    0.05       0  4438.7    0.12       0  4548.1    0.05       0
  5004.8    0.03       0  5010.3    0.05       0  5310.2    0.12       0
  5534.5    0.05       0  5826.3    0.12       0
Bank Sta=5004.8,5010.3
Exp/Cntr=0.3,0.1

Type RM Length L Ch R = 1,1276,343,343,343
BEGIN DESCRIPTION:
Mapping XS aab8494c
END DESCRIPTION:
XS GIS Cut Line= 4
      2810182.26     10253004.65      2809930.50     10253334.55
      2809461.75     10253560.24      2808967.41     10254028.57
#Sta/Elev= 30
  3887.7 1076.76  4011.8 1070.26  4061.9 1070.53  4086.7 1068.02  4127.4 1062.74
  4184.2 1058.87  4205.0 1054.42  4217.4 1053.75  4328.0 1048.19  4380.1 1047.09
  4419.0 1049.18  4453.5 1048.58  4515.9 1053.55  4551.2 1054.43  4611.9 1056.14
  4636.8 1053.61  4699.9 1049.96  4807.5 1046.43  4910.0 1045.67  4956.4 1045.15
  4970.6 1038.53  4996.1 1035.71  4996.5 1035.21  5001.8 1035.71  5077.0 1042.08
  5239.6 1049.69  5282.1 1054.09  5310.4 1054.51  5388.1 1060.33  5503.9 1063.01
#Mann=11,-1,0
  3887.7    0.05       0  4086.7    0.12       0  4127.4    0.05       0
  4217.4    0.12       0  4328.0    0.05       0  4551.2    0.12       0
  4636.8    0.05       0  4699.9    0.12       0  4910.0    0.05       0
  4996.1    0.05       0  5001.8    0.05       0
Bank Sta=4996.1,5001.8
Exp/Cntr=0.3,0.1