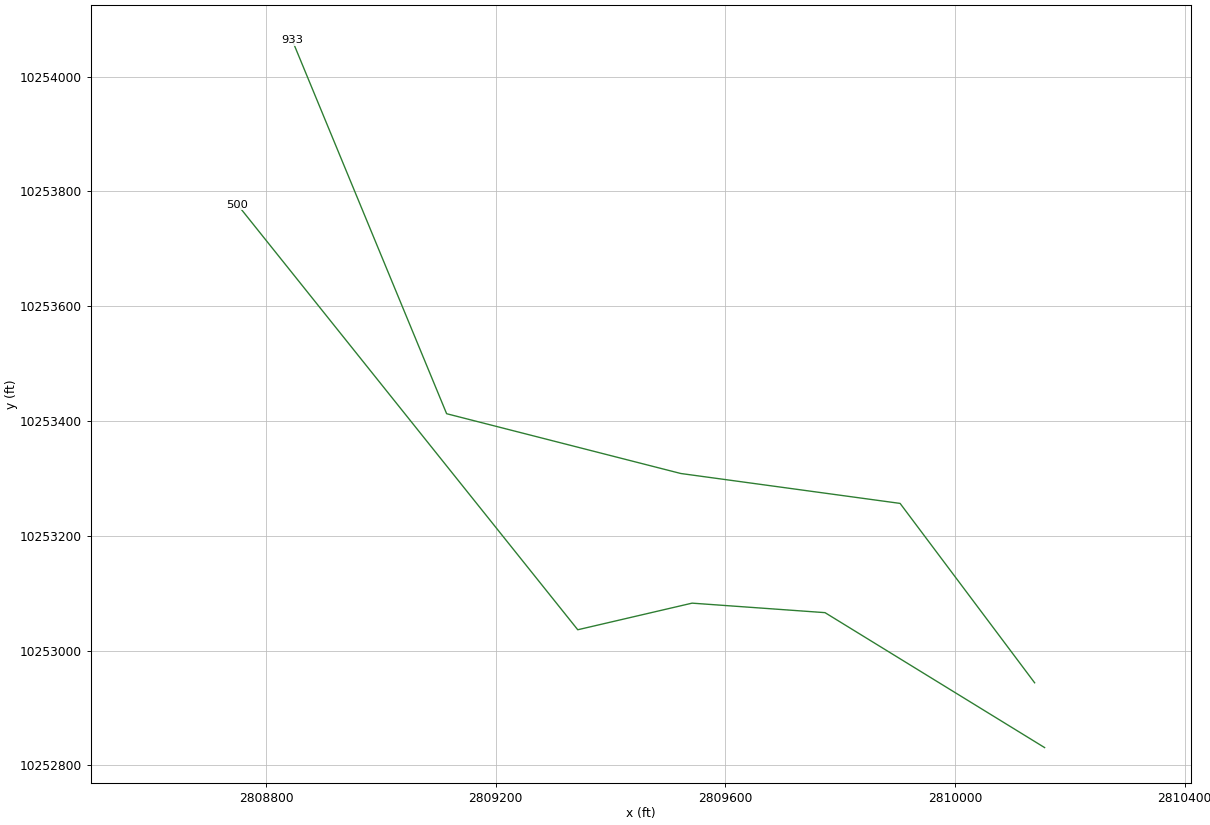
HEC-RAS study SANFERNANDO064.prj: SANFERNANDO064 Base Level Engineering

--- SANFERNANDO064.g01 (geometry) --- (continued)

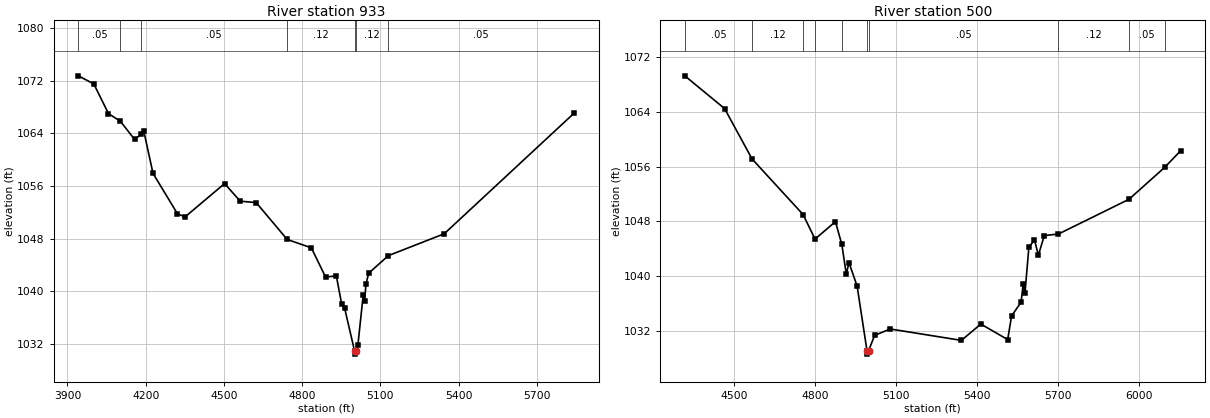
Type RM Length L Ch R = 1,933,433,433,433
BEGIN DESCRIPTION:
Mapping XS 90ef05c2
END DESCRIPTION:
XS GIS Cut Line= 5
      2810138.81     10252943.96      2809904.46     10253256.42
      2809522.51     10253308.51      2809114.53     10253412.67
      2808845.43     10254063.72
#Sta/Elev= 30
  3941.7 1072.75  4001.1 1071.52  4057.3 1067.00  4102.9 1065.84  4157.3 1063.08
  4183.5 1063.86  4192.7 1064.36  4228.1 1057.91  4321.9 1051.76  4351.2 1051.29
  4502.6 1056.36  4562.5 1053.68  4623.7 1053.47  4742.5 1047.86  4835.3 1046.58
  4889.9 1042.14  4931.2 1042.31  4951.9 1037.97  4963.0 1037.40  5001.0 1030.91
  5001.5 1030.41  5006.7 1030.91  5013.8 1031.74  5034.4 1039.48  5039.6 1038.49
  5044.8 1041.04  5055.1 1042.71  5130.5 1045.39  5344.9 1048.72  5843.3 1067.08
#Mann=7,-1,0
  3941.7    0.05       0  4102.9    0.12       0  4183.5    0.05       0
  4742.5    0.12       0  5001.0    0.07       0  5006.7    0.12       0
  5130.5    0.05       0
Bank Sta=5001,5006.7
Exp/Cntr=0.3,0.1

Type RM Length L Ch R = 1,500,0,0,0
BEGIN DESCRIPTION:
SANFERNANDO064 1.0
END DESCRIPTION:
XS GIS Cut Line= 5
      2810156.18     10252831.09      2809773.68     10253066.13
      2809542.11     10253082.68      2809342.96     10253036.33
      2808750.32     10253776.79
#Sta/Elev= 30
  4318.9 1069.28  4466.1 1064.49  4567.7 1057.12  4756.4 1048.99  4800.6 1045.40
  4876.1 1047.95  4899.7 1044.62  4916.2 1040.28  4926.2 1041.95  4956.3 1038.52
  4992.8 1029.07  4993.3 1028.57  4998.6 1029.07  5021.1 1031.31  5078.5 1032.25
  5341.9 1030.58  5413.9 1032.97  5513.2 1030.70  5527.6 1034.15  5562.8 1036.17
  5570.8 1038.88  5577.2 1037.51  5591.6 1044.21  5612.4 1045.28  5626.8 1043.03
  5648.6 1045.91  5701.0 1046.14  5961.9 1051.22  6094.2 1055.90  6152.9 1058.32
#Mann=10,-1,0
  4318.9    0.05       0  4567.7    0.12       0  4756.4    0.05       0
  4800.6    0.12       0  4899.7    0.05       0  4992.8    0.05       0
  4998.6    0.05       0  5701.0    0.12       0  5961.9    0.05       0
  6094.2    0.12       0
Bank Sta=4992.8,4998.6
Exp/Cntr=0.3,0.1

Chan Stop Cuts=-1