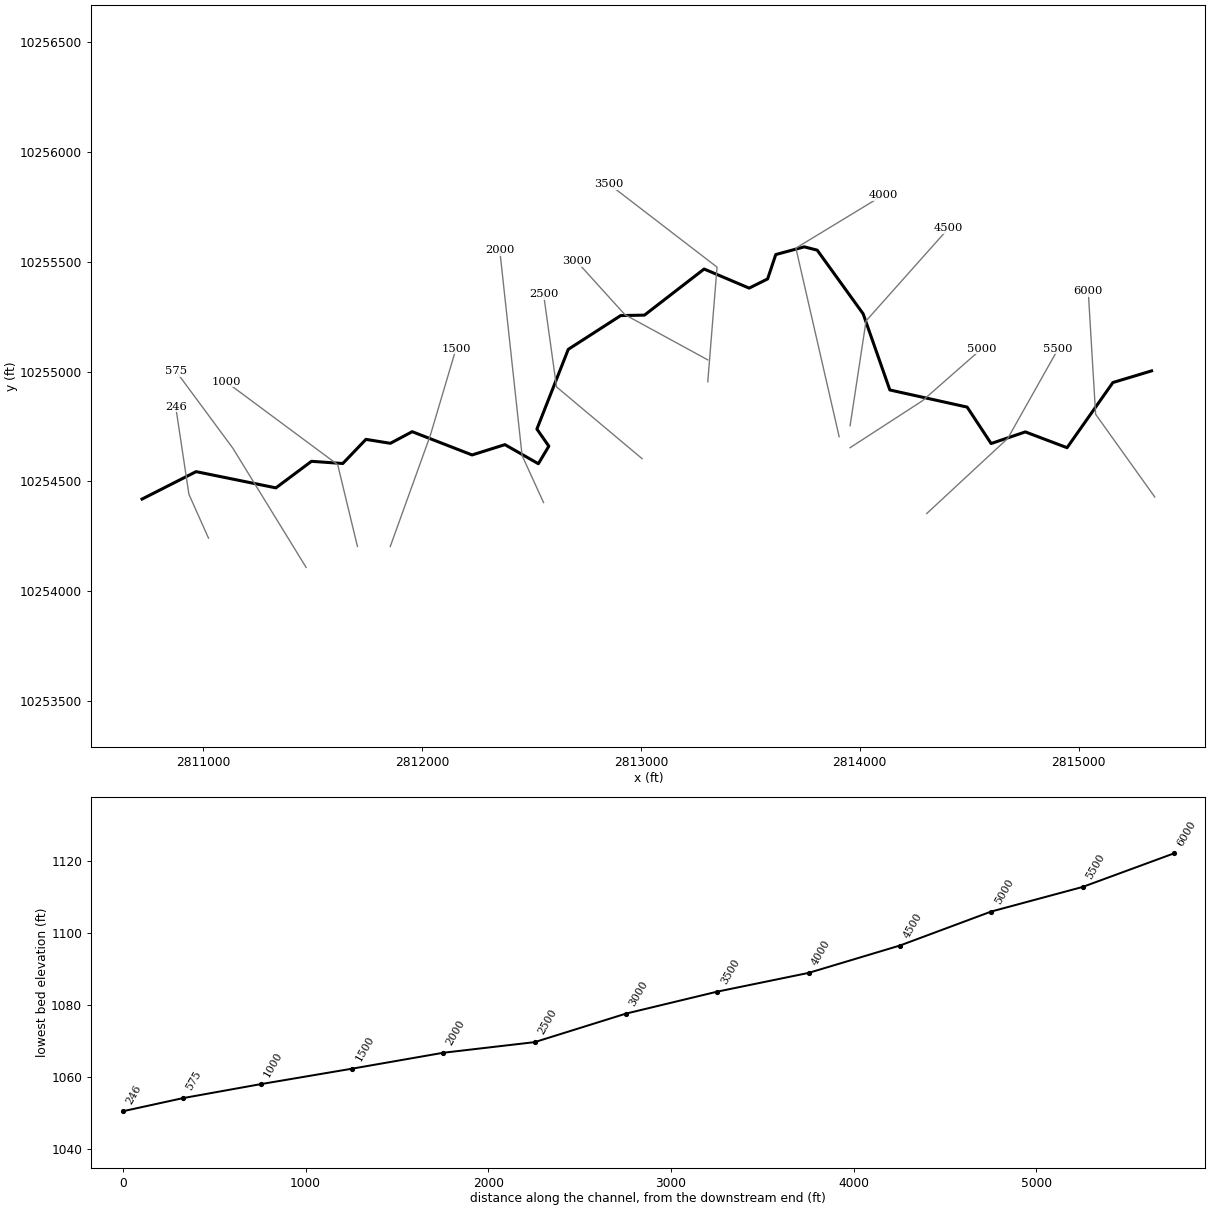
--- SANFERNANDO065.prj (project) ---

Proj Title=SANFERNANDO065 Base Level Engineering
Current Plan=p01
Default Exp/Contr=0.3,0.1
English Units
Geom File=g01
Flow File=f01
Plan File=p01
BEGIN DESCRIPTION:
SANFERNANDO065
END DESCRIPTION:

--- SANFERNANDO065.p01 (plan) ---

Plan Title=Multiple Run
Short Identifier=Multiple
Geom File=g01
Flow File=f01
Subcritical Flow
K Sum by GR= 0
Std Step Tol= 0.01
Critical Tol= 0.01
Num of Std Step Trials= 20
Max Error Tol= 0.3
Flow Tol Ratio= 0.001
Split Flow NTrial= 30
Split Flow Tol= 0.02
Split Flow Ratio= 0.02
Log Output Level= 0
Friction Slope Method= 1
Unsteady Friction Slope Method= 2
Unsteady Bridges Friction Slope Method= 1
Parabolic Critical Depth
Global Vel Dist=  1 , 1 , 1
Global Log Level= 0
CheckData=True
Encroach Param= -1, 0, 0, 0
BEGIN DESCRIPTION:
Multiple Run
END DESCRIPTION:

--- SANFERNANDO065.f01 (steady flow) ---

Flow Title=Multiple
Number of Profiles=7
Profile Names=10-year,25-year,50-year,1pct_min,100-year,1pct_plu,500-year
River Rch & RM= SANFERNANDO065,Reach-1,6000
     239     372     465     288     604    1266     832
Boundary for River Rch & Prof#=SANFERNANDO065,Reach-1,1
Up Type=0
Dn Type=3
Dn Slope=0.005
Boundary for River Rch & Prof#=SANFERNANDO065,Reach-1,2
Up Type=0
Dn Type=3
Dn Slope=0.005
Boundary for River Rch & Prof#=SANFERNANDO065,Reach-1,3
Up Type=0
Dn Type=3
Dn Slope=0.005
Boundary for River Rch & Prof#=SANFERNANDO065,Reach-1,4
Up Type=0
Dn Type=3
Dn Slope=0.005
Boundary for River Rch & Prof#=SANFERNANDO065,Reach-1,5
Up Type=0
Dn Type=3
Dn Slope=0.005
Boundary for River Rch & Prof#=SANFERNANDO065,Reach-1,6
Up Type=0
Dn Type=3
Dn Slope=0.005
Boundary for River Rch & Prof#=SANFERNANDO065,Reach-1,7
Up Type=0
Dn Type=3
Dn Slope=0.005

--- SANFERNANDO065.g01 (geometry) ---

Geom Title=Existing Conditions

River Reach=SANFERNANDO065,Reach-1
Reach XY= 30
      2815332.50     10255003.00      2815156.00     10254950.00
      2814946.50     10254653.00      2814756.00     10254725.00
      2814599.75     10254672.00      2814490.25     10254838.00
      2814137.25     10254916.00      2814015.25     10255263.00
      2813805.50     10255553.00      2813746.50     10255568.00
      2813616.25     10255533.00      2813579.00     10255422.00
      2813494.75     10255380.00      2813289.00     10255467.00
      2813016.50     10255257.00      2812908.00     10255255.00
      2812668.50     10255101.00      2812525.25     10254738.00
      2812579.75     10254660.00      2812532.00     10254580.00
      2812379.25     10254667.00      2812229.25     10254620.00
      2811955.75     10254726.00      2811856.00     10254673.00
      2811744.50     10254691.00      2811638.75     10254581.00
      2811495.75     10254591.00      2811333.25     10254470.00
      2810968.75     10254544.00      2810722.00     10254419.00

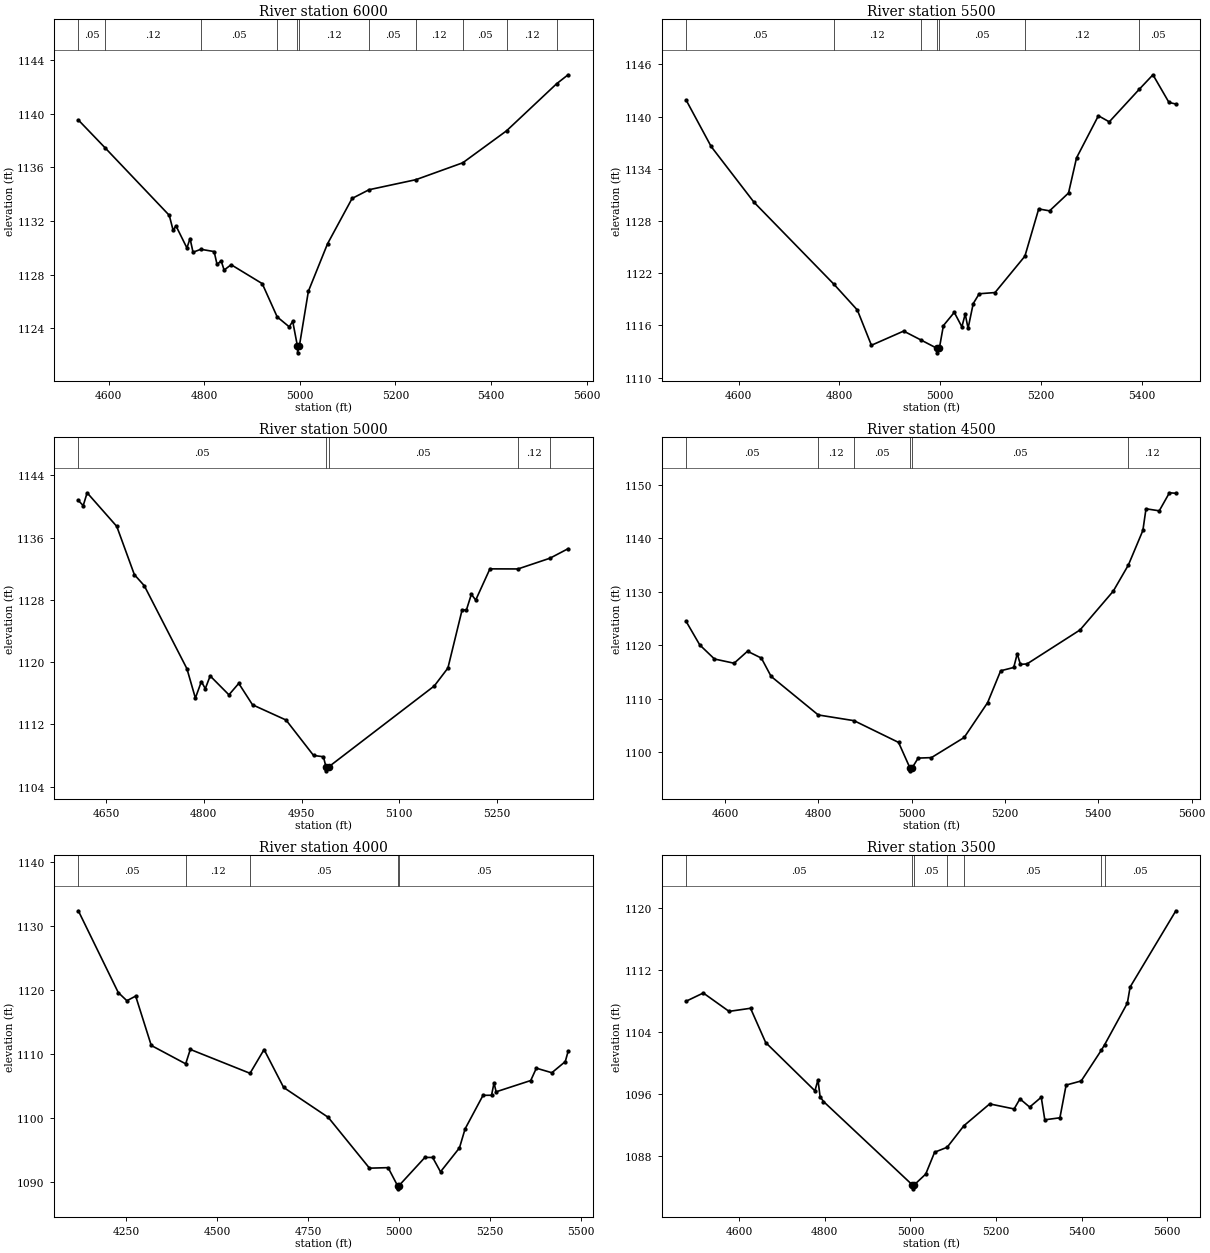
Type RM Length L Ch R = 1,6000,500,500,500
BEGIN DESCRIPTION:
SANFERNANDO065 12.0
END DESCRIPTION:
XS GIS Cut Line= 3
      2815347.17     10254428.29      2815077.01     10254805.41
      2815043.35     10255365.80
#Sta/Elev= 30
  4536.1 1139.54  4592.5 1137.45  4726.5 1132.43  4734.4 1131.33  4740.6 1131.64
  4763.4 1130.00  4770.0 1130.70  4776.2 1129.68  4792.5 1129.90  4820.4 1129.73
  4826.5 1128.77  4835.1 1129.04  4841.3 1128.35  4856.0 1128.75  4921.1 1127.34
  4952.4 1124.86  4977.6 1124.12  4984.9 1124.53  4994.8 1122.68  4995.1 1122.18
  4998.8 1122.68  5017.7 1126.77  5057.8 1130.31  5109.2 1133.69  5144.7 1134.34
  5242.9 1135.09  5341.0 1136.35  5432.5 1138.73  5537.4 1142.24  5561.4 1142.91
#Mann=11,-1,0
  4536.1    0.05       0  4592.5    0.12       0  4792.5    0.05       0
  4952.4    0.12       0  4994.8    0.07       0  4998.8    0.12       0
  5144.7    0.05       0  5242.9    0.12       0  5341.0    0.05       0
  5432.5    0.12       0  5537.4    0.05       0
Bank Sta=4994.8,4998.8
Exp/Cntr=0.3,0.1

Type RM Length L Ch R = 1,5500,500,500,500
BEGIN DESCRIPTION:
SANFERNANDO065 11.0
END DESCRIPTION:
XS GIS Cut Line= 3
      2814305.68     10254353.10      2814675.69     10254695.31
      2814905.69     10255103.12
#Sta/Elev= 30
  4496.0 1141.90  4545.6 1136.57  4630.7 1130.16  4789.8 1120.71  4835.9 1117.77
  4863.8 1113.72  4927.8 1115.35  4961.7 1114.34  4994.6 1113.35  4994.8 1112.85
  4998.6 1113.35  5006.7 1115.98  5028.3 1117.50  5043.4 1115.84  5050.0 1117.31
  5055.7 1115.66  5065.9 1118.51  5077.8 1119.64  5109.2 1119.78  5168.5 1123.96
  5195.9 1129.39  5217.5 1129.17  5255.1 1131.22  5271.0 1135.26  5314.4 1140.10
  5336.0 1139.40  5395.3 1143.13  5422.7 1144.81  5454.5 1141.63  5468.2 1141.45
#Mann=7,-1,0
  4496.0    0.05       0  4789.8    0.12       0  4961.7    0.05       0
  4994.6    0.05       0  4998.6    0.05       0  5168.5    0.12       0
  5395.3    0.05       0
Bank Sta=4994.6,4998.6
Exp/Cntr=0.3,0.1

Type RM Length L Ch R = 1,5000,500,500,500
BEGIN DESCRIPTION:
SANFERNANDO065 10.0
END DESCRIPTION:
XS GIS Cut Line= 3
      2813955.73     10254653.14      2814285.50     10254866.35
      2814555.65     10255103.09
#Sta/Elev= 30
  4607.3 1140.77  4614.8 1140.11  4620.8 1141.76  4666.3 1137.44  4693.3 1131.24
  4708.5 1129.82  4774.0 1119.15  4787.0 1115.37  4796.2 1117.50  4802.2 1116.58
  4809.7 1118.22  4838.5 1115.79  4853.6 1117.26  4874.7 1114.51  4926.2 1112.55
  4968.4 1108.00  4983.6 1107.83  4987.5 1106.52  4987.8 1106.02  4991.5 1106.52
  5153.8 1116.93  5174.7 1119.23  5196.5 1126.71  5203.1 1126.69  5210.7 1128.71
  5217.4 1127.97  5239.2 1131.98  5282.3 1131.97  5331.4 1133.35  5359.2 1134.57
#Mann=5,-1,0
  4607.3    0.05       0  4987.5    0.05       0  4991.5    0.05       0
  5282.3    0.12       0  5331.4    0.05       0
Bank Sta=4987.5,4991.5
Exp/Cntr=0.3,0.1

Type RM Length L Ch R = 1,4500,500,500,500
BEGIN DESCRIPTION:
SANFERNANDO065 9.0
END DESCRIPTION:
XS GIS Cut Line= 3
      2813955.69     10254753.13      2814028.60     10255230.80
      2814405.71     10255653.14
#Sta/Elev= 30
  4516.8 1124.48  4546.0 1120.09  4577.5 1117.46  4619.6 1116.67  4648.3 1118.91
  4678.0 1117.63  4698.9 1114.21  4799.9 1107.01  4876.6 1105.94  4972.0 1101.88
  4996.6 1097.07  4996.9 1096.57  5000.6 1097.07  5014.0 1098.95  5042.4 1099.04
  5112.6 1102.80  5162.8 1109.31  5190.8 1115.26  5218.8 1115.88  5226.3 1118.45
  5233.0 1116.46  5247.2 1116.54  5360.9 1122.89  5432.0 1130.13  5464.4 1135.01
  5495.5 1141.47  5502.2 1145.52  5530.6 1145.14  5552.4 1148.51  5566.2 1148.42
#Mann=6,-1,0
  4516.8    0.05       0  4799.9    0.12       0  4876.6    0.05       0
  4996.6    0.05       0  5000.6    0.05       0  5464.4    0.12       0
Bank Sta=4996.6,5000.6
Exp/Cntr=0.3,0.1

Type RM Length L Ch R = 1,4000,500,500,500
BEGIN DESCRIPTION:
SANFERNANDO065 8.0
END DESCRIPTION:
XS GIS Cut Line= 3
      2813905.69     10254703.09      2813708.12     10255562.27
      2814105.66     10255803.10
#Sta/Elev= 30
  4118.4 1132.40  4228.1 1119.63  4251.8 1118.35  4276.0 1119.07  4318.9 1111.36
  4413.5 1108.49  4426.2 1110.74  4590.4 1107.01  4629.0 1110.72  4682.8 1104.80
  4805.4 1100.13  4918.8 1092.19  4970.1 1092.27  4995.9 1089.46  4996.1 1088.96
  4999.9 1089.46  5071.2 1093.87  5092.5 1093.86  5114.1 1091.62  5166.2 1095.36
  5181.7 1098.33  5231.0 1103.57  5254.4 1103.58  5261.2 1105.50  5267.0 1104.12
  5362.1 1105.88  5377.6 1107.81  5420.2 1107.10  5457.1 1108.84  5464.8 1110.42
#Mann=5,-1,0
  4118.4    0.05       0  4413.5    0.12       0  4590.4    0.05       0
  4995.9    0.05       0  4999.9    0.05       0
Bank Sta=4995.9,4999.9
Exp/Cntr=0.3,0.1

Type RM Length L Ch R = 1,3500,500,500,500
BEGIN DESCRIPTION:
SANFERNANDO065 7.0
END DESCRIPTION:
XS GIS Cut Line= 3
      2813305.68     10254953.12      2813347.93     10255475.62
      2812855.71     10255853.09
#Sta/Elev= 30
  4475.8 1107.94  4515.9 1109.00  4576.1 1106.63  4626.3 1107.03  4661.7 1102.61
  4776.8 1096.39  4783.9 1097.80  4788.9 1095.62  4796.8 1095.01  5004.6 1084.25
  5004.9 1083.75  5008.6 1084.25  5035.7 1085.65  5056.5 1088.47  5085.8 1089.11
  5125.0 1091.89  5185.2 1094.70  5242.3 1094.05  5255.9 1095.35  5278.6 1094.29
  5305.7 1095.56  5314.0 1092.65  5349.3 1092.91  5363.8 1097.13  5399.1 1097.66
  5446.2 1101.63  5453.6 1102.31  5506.9 1107.69  5513.4 1109.77  5620.3 1119.60
#Mann=7,-1,0
  4475.8    0.05       0  5004.6    0.05       0  5008.6    0.05       0
  5085.8    0.12       0  5125.0    0.05       0  5446.2    0.12       0
  5453.6    0.05       0
Bank Sta=5004.6,5008.6
Exp/Cntr=0.3,0.1

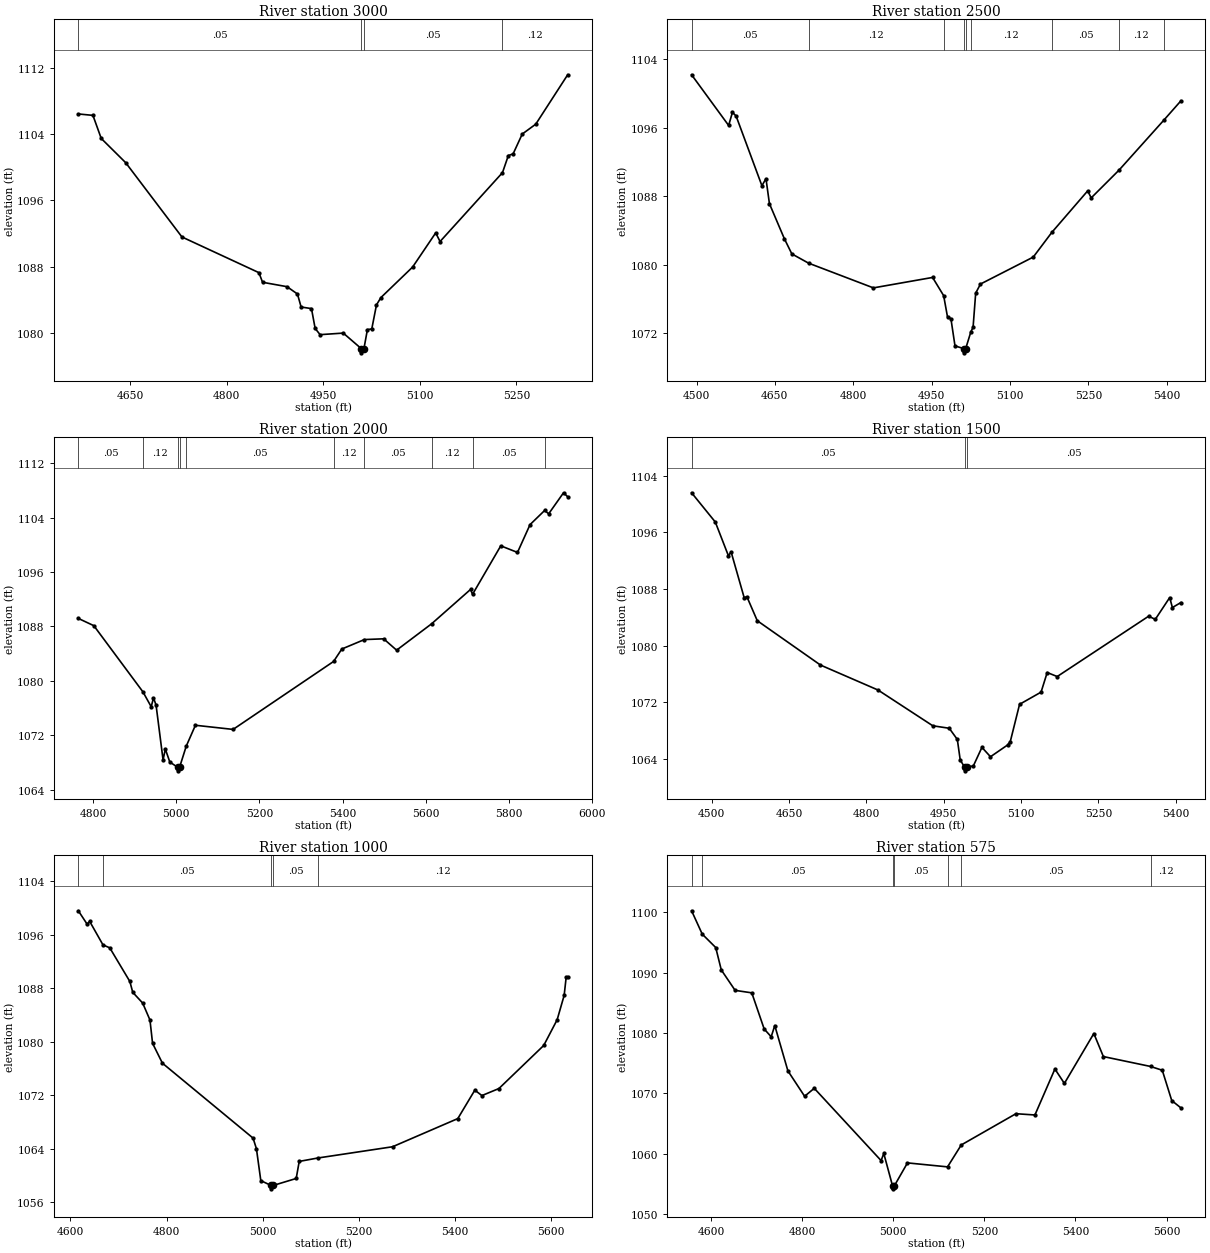
Type RM Length L Ch R = 1,3000,500,500,500
BEGIN DESCRIPTION:
SANFERNANDO065 6.0
END DESCRIPTION:
XS GIS Cut Line= 3
      2813305.65     10255053.13      2812927.33     10255259.00
      2812705.70     10255503.09
#Sta/Elev= 30
  4569.3 1106.42  4592.0 1106.25  4604.9 1103.47  4642.9 1100.55  4730.3 1091.60
  4849.9 1087.30  4855.6 1086.14  4893.6 1085.61  4909.8 1084.73  4915.5 1083.16
  4931.6 1082.97  4937.3 1080.58  4945.0 1079.83  4981.0 1080.02  5009.1 1078.14
  5009.3 1077.64  5013.1 1078.14  5018.5 1080.44  5025.3 1080.52  5032.6 1083.42
  5039.5 1084.30  5088.8 1087.98  5124.6 1092.09  5131.4 1091.05  5228.4 1099.35
  5237.5 1101.41  5244.9 1101.61  5259.1 1104.00  5280.1 1105.19  5329.7 1111.14
#Mann=4,-1,0
  4569.3    0.05       0  5009.1    0.05       0  5013.1    0.05       0
  5228.4    0.12       0
Bank Sta=5009.1,5013.1
Exp/Cntr=0.3,0.1

Type RM Length L Ch R = 1,2500,500,500,500
BEGIN DESCRIPTION:
SANFERNANDO065 5.0
END DESCRIPTION:
XS GIS Cut Line= 3
      2813005.65     10254603.14      2812614.89     10254929.93
      2812555.68     10255353.11
#Sta/Elev= 30
  4490.6 1102.20  4561.5 1096.28  4568.8 1097.81  4575.8 1097.38  4625.2 1089.24
  4633.0 1090.06  4639.6 1087.14  4668.2 1083.04  4682.5 1081.27  4714.5 1080.19
  4838.6 1077.30  4951.9 1078.52  4973.1 1076.39  4980.5 1073.89  4987.0 1073.70
  4994.8 1070.52  5011.3 1070.21  5011.6 1069.71  5015.3 1070.21  5025.2 1072.17
  5029.4 1072.69  5034.4 1076.69  5043.6 1077.75  5144.6 1080.90  5180.1 1083.78
  5248.7 1088.63  5255.6 1087.82  5308.8 1091.06  5394.0 1096.86  5427.3 1099.16
#Mann=9,-1,0
  4490.6    0.05       0  4714.5    0.12       0  4973.1    0.05       0
  5011.3    0.05       0  5015.3    0.05       0  5025.2    0.12       0
  5180.1    0.05       0  5308.8    0.12       0  5394.0    0.05       0
Bank Sta=5011.3,5015.3
Exp/Cntr=0.3,0.1

Type RM Length L Ch R = 1,2000,500,500,500
BEGIN DESCRIPTION:
SANFERNANDO065 4.0
END DESCRIPTION:
XS GIS Cut Line= 3
      2812555.68     10254403.11      2812457.67     10254617.14
      2812355.69     10255553.10
#Sta/Elev= 30
  4764.6 1089.17  4801.9 1088.10  4920.0 1078.37  4939.9 1076.18  4945.4 1077.49
  4951.6 1076.42  4968.4 1068.37  4973.9 1069.96  4984.6 1068.06  5004.0 1067.26
  5004.3 1066.76  5008.0 1067.26  5024.1 1070.38  5046.2 1073.46  5136.8 1072.85
  5378.5 1082.84  5398.3 1084.67  5452.6 1086.06  5498.9 1086.17  5530.1 1084.50
  5614.3 1088.38  5707.9 1093.43  5712.7 1092.71  5780.6 1099.84  5820.8 1098.87
  5851.0 1102.96  5886.1 1105.04  5895.8 1104.55  5931.5 1107.64  5941.5 1107.06
#Mann=10,-1,0
  4764.6    0.05       0  4920.0    0.12       0  5004.0    0.07       0
  5008.0    0.12       0  5024.1    0.05       0  5378.5    0.12       0
  5452.6    0.05       0  5614.3    0.12       0  5712.7    0.05       0
  5886.1    0.12       0
Bank Sta=5004,5008
Exp/Cntr=0.3,0.1

Type RM Length L Ch R = 1,1500,500,500,500
BEGIN DESCRIPTION:
SANFERNANDO065 3.0
END DESCRIPTION:
XS GIS Cut Line= 3
      2811855.68     10254203.11      2812038.77     10254709.96
      2812155.69     10255103.14
#Sta/Elev= 30
  4461.1 1101.58  4507.1 1097.45  4532.4 1092.71  4537.8 1093.22  4563.1 1086.77
  4568.4 1086.90  4588.5 1083.52  4711.1 1077.26  4822.6 1073.74  4928.9 1068.69
  4960.8 1068.34  4976.5 1066.76  4982.1 1063.87  4990.7 1062.83  4991.0 1062.33
  4994.7 1062.83  5007.6 1063.03  5024.2 1065.64  5040.8 1064.32  5074.0 1065.98
  5079.2 1066.46  5097.2 1071.72  5138.9 1073.44  5150.8 1076.21  5170.2 1075.64
  5347.6 1084.16  5360.4 1083.71  5388.4 1086.79  5393.6 1085.38  5410.2 1086.09
#Mann=3,-1,0
  4461.1    0.05       0  4990.7    0.05       0  4994.7    0.05       0
Bank Sta=4990.7,4994.7
Exp/Cntr=0.3,0.1

Type RM Length L Ch R = 1,1000,425,425,425
BEGIN DESCRIPTION:
SANFERNANDO065 2.0
END DESCRIPTION:
XS GIS Cut Line= 3
      2811705.69     10254203.08      2811615.52     10254575.73
      2811105.69     10254953.10
#Sta/Elev= 30
  4616.6 1099.59  4635.0 1097.58  4640.1 1098.02  4667.9 1094.49  4682.0 1094.05
  4723.8 1089.02  4729.8 1087.40  4750.4 1085.80  4765.6 1083.26  4771.0 1079.78
  4791.5 1076.81  4980.0 1065.61  4987.0 1064.03  4996.1 1059.26  5017.6 1058.53
  5017.9 1058.03  5021.6 1058.53  5069.7 1059.58  5076.0 1062.13  5114.8 1062.64
  5270.1 1064.32  5405.8 1068.53  5441.2 1072.78  5455.9 1071.97  5491.3 1073.02
  5584.5 1079.46  5612.4 1083.30  5627.0 1086.95  5631.2 1089.69  5634.3 1089.69
#Mann=5,-1,0
  4616.6    0.12       0  4667.9    0.05       0  5017.6    0.05       0
  5021.6    0.05       0  5114.8    0.12       0
Bank Sta=5017.6,5021.6
Exp/Cntr=0.3,0.1

Type RM Length L Ch R = 1,575,329,329,329
BEGIN DESCRIPTION:
Mapping XS 7e320678
END DESCRIPTION:
XS GIS Cut Line= 3
      2811471.31     10254107.58      2811137.11     10254650.11
      2810876.70     10255001.67
#Sta/Elev= 30
  4556.9 1100.23  4580.3 1096.36  4609.9 1094.14  4622.1 1090.43  4652.5 1087.04
  4689.1 1086.63  4716.3 1080.64  4731.7 1079.35  4739.6 1081.21  4768.4 1073.70
  4805.1 1069.49  4826.3 1070.81  4973.1 1058.83  4979.0 1060.01  4998.2 1054.65
  4998.5 1054.15  5002.2 1054.65  5031.0 1058.45  5119.0 1057.79  5149.1 1061.42
  5269.2 1066.60  5310.9 1066.39  5354.8 1074.01  5375.6 1071.62  5440.3 1079.89
  5461.2 1076.07  5564.9 1074.43  5590.6 1073.80  5611.4 1068.78  5631.6 1067.56
#Mann=7,-1,0
  4556.9    0.12       0  4580.3    0.05       0  4998.2    0.05       0
  5002.2    0.05       0  5119.0    0.12       0  5149.1    0.05       0
  5564.9    0.12       0
Bank Sta=4998.2,5002.2
Exp/Cntr=0.3,0.1

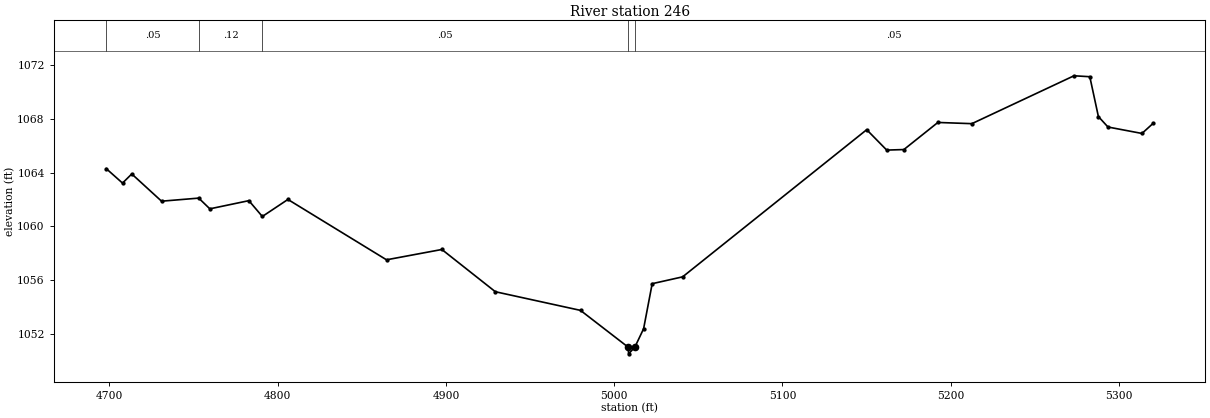
Type RM Length L Ch R = 1,246,0,0,0
BEGIN DESCRIPTION:
SANFERNANDO065 1.0
END DESCRIPTION:
XS GIS Cut Line= 3
      2811025.48     10254241.04      2810936.06     10254440.67
      2810875.71     10254839.59
#Sta/Elev= 30
  4698.1 1064.31  4707.8 1063.23  4713.3 1063.91  4731.0 1061.88  4753.1 1062.11
  4759.7 1061.31  4782.9 1061.92  4790.9 1060.74  4806.1 1062.01  4864.7 1057.51
  4897.6 1058.28  4929.4 1055.13  4980.0 1053.74  5008.3 1051.00  5008.6 1050.50
  5012.3 1051.00  5017.5 1052.37  5022.6 1055.73  5040.7 1056.24  5150.1 1067.21
  5162.0 1065.69  5172.2 1065.73  5192.4 1067.75  5212.6 1067.66  5273.3 1071.23
  5282.7 1071.16  5287.8 1068.19  5293.5 1067.41  5313.7 1066.93  5320.3 1067.68
#Mann=5,-1,0
  4698.1    0.05       0  4753.1    0.12       0  4790.9    0.05       0
  5008.3    0.05       0  5012.3    0.05       0
Bank Sta=5008.3,5012.3
Exp/Cntr=0.3,0.1

Chan Stop Cuts=-1