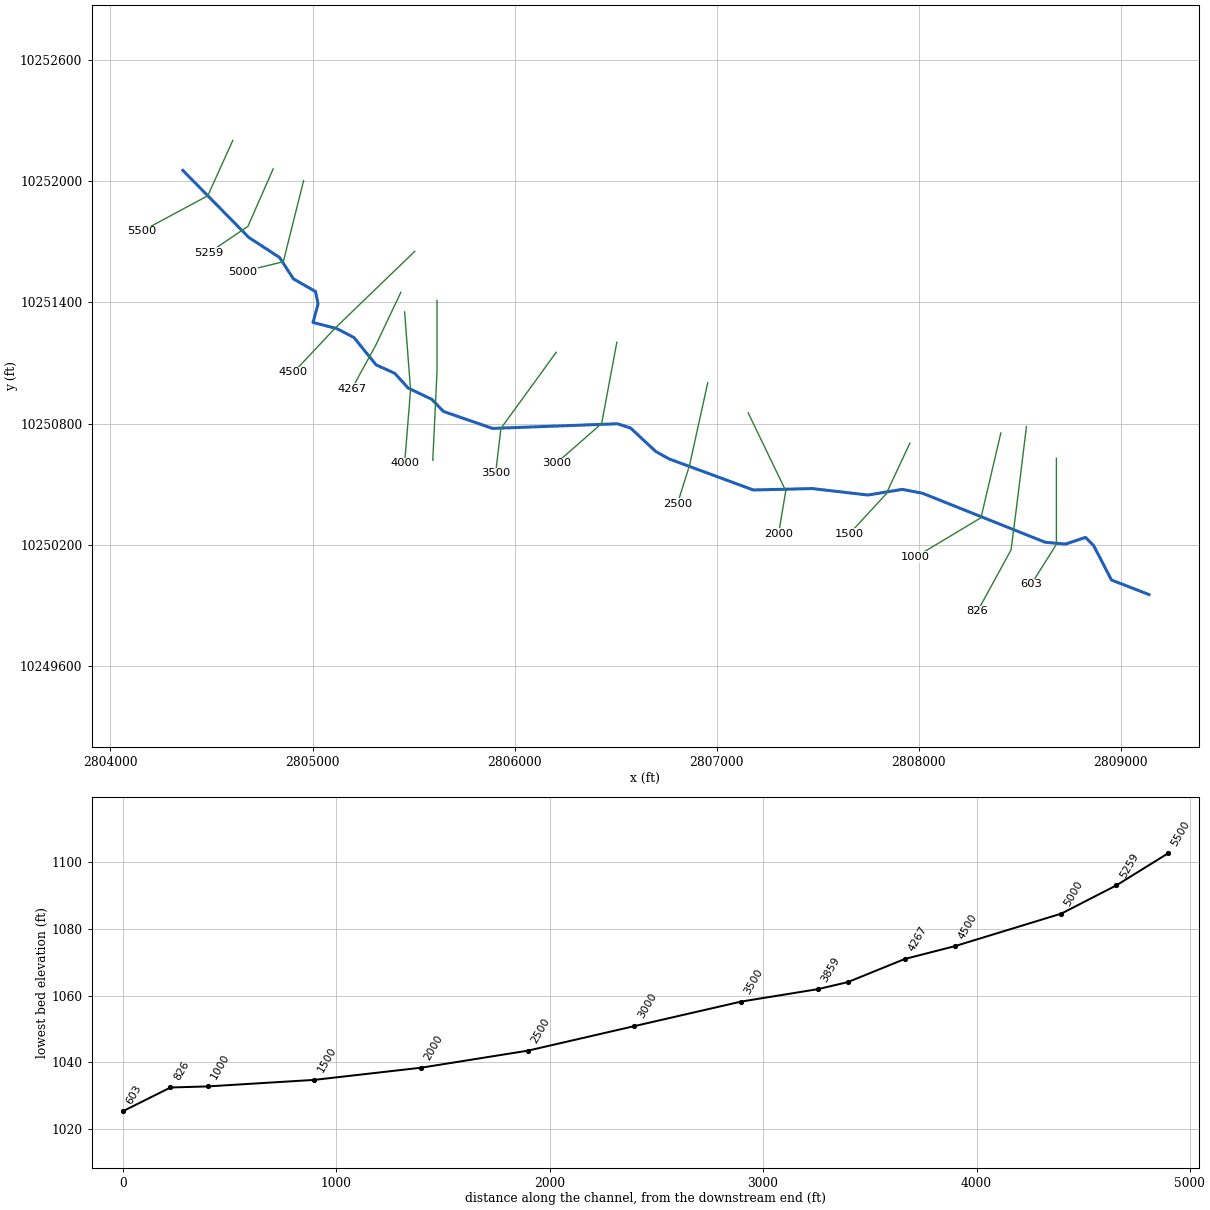
--- SANFERNANDO066.prj (project) ---

Proj Title=SANFERNANDO066 Base Level Engineering
Current Plan=p01
Default Exp/Contr=0.3,0.1
English Units
Geom File=g01
Flow File=f01
Plan File=p01
BEGIN DESCRIPTION:
SANFERNANDO066
END DESCRIPTION:

--- SANFERNANDO066.p01 (plan) ---

Plan Title=Multiple Run
Short Identifier=Multiple
Geom File=g01
Flow File=f01
Subcritical Flow
K Sum by GR= 0
Std Step Tol= 0.01
Critical Tol= 0.01
Num of Std Step Trials= 20
Max Error Tol= 0.3
Flow Tol Ratio= 0.001
Split Flow NTrial= 30
Split Flow Tol= 0.02
Split Flow Ratio= 0.02
Log Output Level= 0
Friction Slope Method= 1
Unsteady Friction Slope Method= 2
Unsteady Bridges Friction Slope Method= 1
Parabolic Critical Depth
Global Vel Dist=  1 , 1 , 1
Global Log Level= 0
CheckData=True
Encroach Param= -1, 0, 0, 0
BEGIN DESCRIPTION:
Multiple Run
END DESCRIPTION:

--- SANFERNANDO066.f01 (steady flow) ---

Flow Title=Multiple
Number of Profiles=7
Profile Names=10-year,25-year,50-year,1pct_min,100-year,1pct_plu,500-year
River Rch & RM= SANFERNANDO066,Reach-1,5500
     167     255     350     216     456     963     639
River Rch & RM= SANFERNANDO066,Reach-1,2500
     279     440     609     423     806    1534    1123
Boundary for River Rch & Prof#=SANFERNANDO066,Reach-1,1
Up Type=0
Dn Type=3
Dn Slope=0.005
Boundary for River Rch & Prof#=SANFERNANDO066,Reach-1,2
Up Type=0
Dn Type=3
Dn Slope=0.005
Boundary for River Rch & Prof#=SANFERNANDO066,Reach-1,3
Up Type=0
Dn Type=3
Dn Slope=0.005
Boundary for River Rch & Prof#=SANFERNANDO066,Reach-1,4
Up Type=0
Dn Type=3
Dn Slope=0.005
Boundary for River Rch & Prof#=SANFERNANDO066,Reach-1,5
Up Type=0
Dn Type=3
Dn Slope=0.005
Boundary for River Rch & Prof#=SANFERNANDO066,Reach-1,6
Up Type=0
Dn Type=3
Dn Slope=0.005
Boundary for River Rch & Prof#=SANFERNANDO066,Reach-1,7
Up Type=0
Dn Type=3
Dn Slope=0.005

--- SANFERNANDO066.g01 (geometry) ---

Geom Title=Existing Conditions

River Reach=SANFERNANDO066,Reach-1
Reach XY= 30
      2804358.50     10252054.00      2804684.75     10251722.00
      2804836.50     10251623.00      2804905.25     10251517.00
      2805014.75     10251454.00      2805027.25     10251392.00
      2805002.25     10251301.00      2805121.00     10251270.00
      2805205.25     10251226.00      2805314.25     10251091.00
      2805406.75     10251049.00      2805473.00     10250976.00
      2805590.25     10250920.00      2805647.75     10250860.00
      2805890.75     10250776.00      2806509.00     10250799.00
      2806573.50     10250778.00      2806698.00     10250662.00
      2806764.00     10250625.00      2807181.00     10250471.00
      2807472.50     10250478.00      2807748.50     10250446.00
      2807917.50     10250474.00      2808017.50     10250455.00
      2808625.25     10250212.00      2808725.75     10250203.00
      2808824.75     10250236.00      2808864.75     10250196.00
      2808953.25     10250025.00      2809138.50     10249953.00

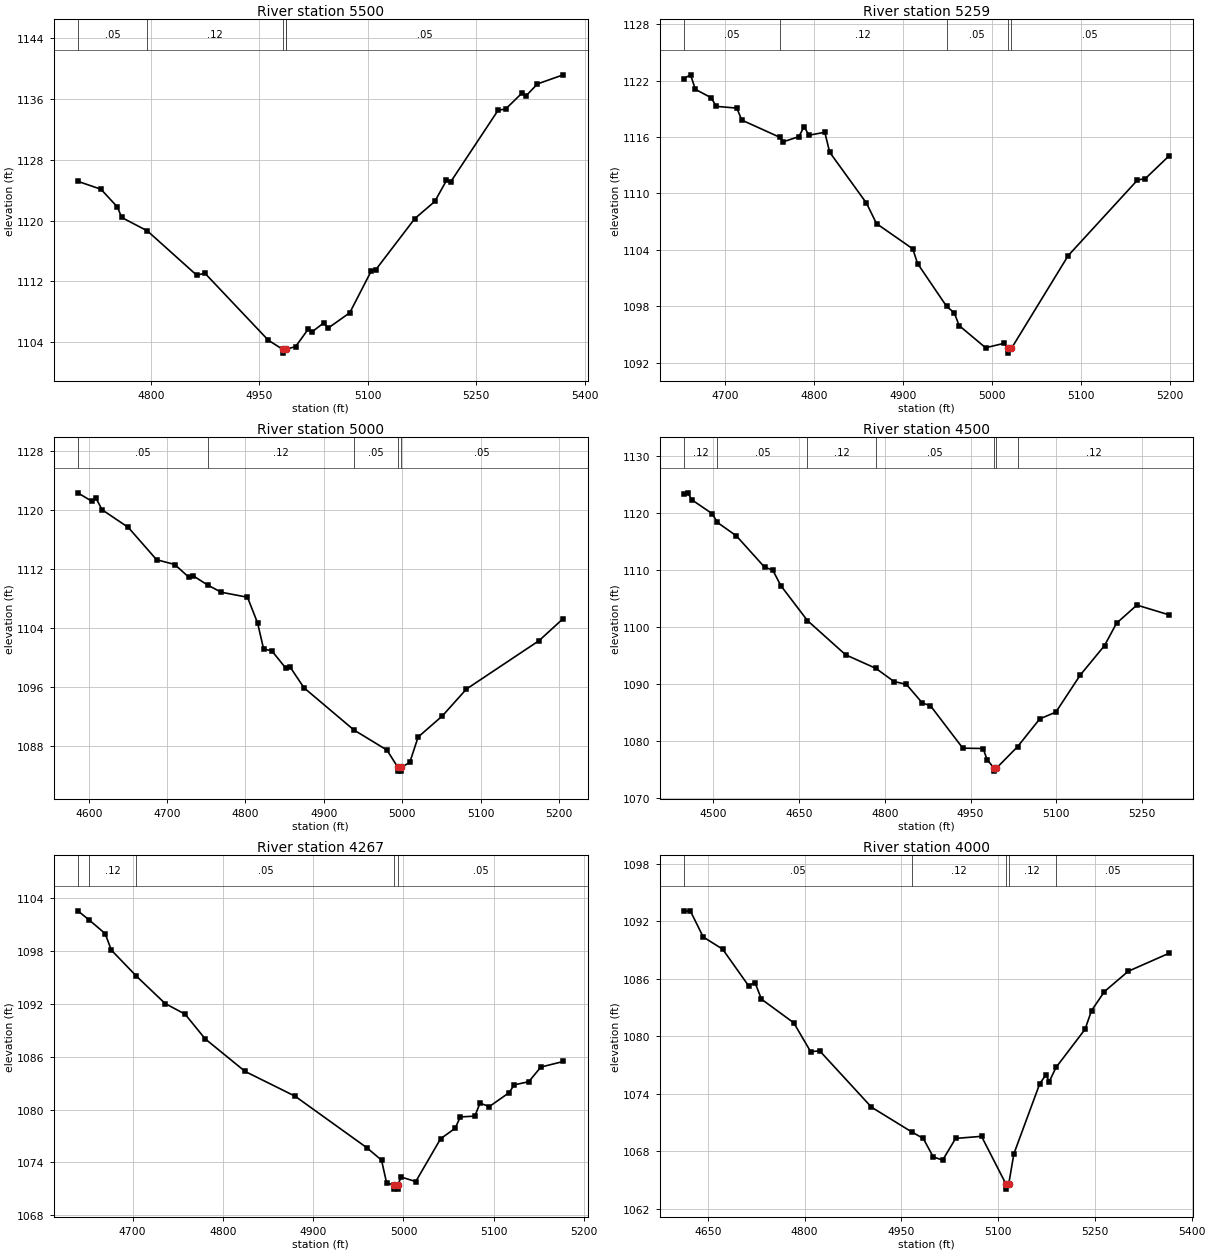
Type RM Length L Ch R = 1,5500,241,241,241
BEGIN DESCRIPTION:
SANFERNANDO066 11.0
END DESCRIPTION:
XS GIS Cut Line= 3
      2804605.69     10252203.13      2804481.68     10251928.65
      2804155.64     10251753.09
#Sta/Elev= 30
  4698.8 1125.17  4730.8 1124.13  4753.7 1121.78  4759.4 1120.42  4795.0 1118.65
  4863.4 1112.81  4874.4 1113.10  4962.2 1104.28  4982.1 1103.07  4982.4 1102.57
  4986.1 1103.07  4986.6 1103.09  5000.0 1103.42  5017.4 1105.71  5023.0 1105.38
  5039.3 1106.57  5044.9 1105.85  5075.0 1107.88  5105.0 1113.43  5110.7 1113.51
  5165.0 1120.27  5192.6 1122.52  5208.8 1125.29  5214.5 1125.08  5280.2 1134.52
  5290.8 1134.69  5312.7 1136.73  5318.3 1136.36  5334.6 1137.98  5370.3 1139.18
#Mann=5,-1,0
  4698.8    0.05       0  4795.0    0.12       0  4982.1    0.05       0
  4986.1    0.12       0  4986.6    0.05       0
Bank Sta=4982.1,4986.1
Exp/Cntr=0.3,0.1

Type RM Length L Ch R = 1,5259,259,259,259
BEGIN DESCRIPTION:
Mapping XS 7a51d9b9
END DESCRIPTION:
XS GIS Cut Line= 3
      2804805.22     10252061.65      2804680.20     10251776.89
      2804485.74     10251644.93
#Sta/Elev= 30
  4653.2 1122.21  4660.8 1122.61  4666.2 1121.07  4684.1 1120.17  4689.6 1119.26
  4712.9 1119.07  4718.4 1117.80  4761.4 1115.96  4765.1 1115.49  4782.7 1116.04
  4788.5 1117.11  4793.9 1116.19  4811.8 1116.50  4817.3 1114.38  4858.6 1108.98
  4870.0 1106.79  4910.7 1104.11  4916.2 1102.54  4948.9 1097.98  4957.4 1097.31
  4962.9 1095.95  4992.7 1093.59  5013.7 1094.07  5017.7 1093.52  5018.0 1093.02
  5021.7 1093.52  5085.6 1103.39  5163.5 1111.42  5172.4 1111.58  5199.2 1114.01
#Mann=5,-1,0
  4653.2    0.05       0  4761.4    0.12       0  4948.9    0.05       0
  5017.7    0.05       0  5021.7    0.05       0
Bank Sta=5017.7,5021.7
Exp/Cntr=0.3,0.1

Type RM Length L Ch R = 1,5000,500,500,500
BEGIN DESCRIPTION:
SANFERNANDO066 10.0
END DESCRIPTION:
XS GIS Cut Line= 3
      2804955.68     10252003.11      2804855.38     10251601.55
      2804655.67     10251553.11
#Sta/Elev= 30
  4586.1 1122.27  4604.1 1121.12  4609.3 1121.55  4617.0 1119.98  4650.5 1117.58
  4686.6 1113.20  4709.8 1112.55  4727.9 1110.81  4733.0 1111.04  4751.7 1109.77
  4769.1 1108.79  4802.6 1108.11  4815.5 1104.62  4823.2 1101.08  4833.5 1100.86
  4851.6 1098.48  4856.8 1098.68  4874.7 1095.83  4938.4 1090.11  4980.5 1087.39
  4994.6 1085.03  4994.9 1084.53  4998.4 1084.53  4998.6 1085.03  5009.7 1085.71
  5020.3 1089.15  5051.1 1092.00  5082.0 1095.66  5174.6 1102.22  5205.5 1105.22
#Mann=5,-1,0
  4586.1    0.05       0  4751.7    0.12       0  4938.4    0.05       0
  4994.6    0.03       0  4998.6    0.05       0
Bank Sta=4994.6,4998.6
Exp/Cntr=0.3,0.1

Type RM Length L Ch R = 1,4500,233,233,233
BEGIN DESCRIPTION:
SANFERNANDO066 9.0
END DESCRIPTION:
XS GIS Cut Line= 3
      2805505.69     10251653.12      2805108.99     10251270.00
      2804905.67     10251053.09
#Sta/Elev= 30
  4448.5 1123.26  4455.6 1123.49  4462.5 1122.27  4498.0 1119.85  4507.4 1118.30
  4540.5 1115.95  4589.9 1110.46  4604.0 1109.98  4618.2 1107.24  4664.8 1101.12
  4731.4 1095.14  4784.2 1092.77  4816.2 1090.45  4837.6 1089.97  4865.6 1086.70
  4879.8 1086.22  4936.4 1078.79  4971.9 1078.73  4978.8 1076.80  4991.0 1075.27
  4991.2 1074.77  4995.0 1075.27  5032.2 1079.06  5070.9 1083.91  5099.2 1085.11
  5141.7 1091.58  5184.2 1096.75  5205.2 1100.66  5240.8 1103.84  5297.3 1102.12
#Mann=7,-1,0
  4448.5    0.12       0  4507.4    0.05       0  4664.8    0.12       0
  4784.2    0.05       0  4991.0    0.05       0  4995.0    0.05       0
  5032.2    0.12       0
Bank Sta=4991,4995
Exp/Cntr=0.3,0.1

Type RM Length L Ch R = 1,4267,267,267,267
BEGIN DESCRIPTION:
Mapping XS 46659f05
END DESCRIPTION:
XS GIS Cut Line= 3
      2805437.14     10251450.50      2805312.15     10251186.61
      2805194.10     10250971.35
#Sta/Elev= 30
  4639.4 1102.57  4652.0 1101.53  4669.7 1099.98  4676.5 1098.11  4704.3 1095.15
  4736.1 1092.04  4758.2 1090.83  4780.4 1088.03  4824.6 1084.33  4879.9 1081.52
  4959.6 1075.65  4975.7 1074.25  4981.4 1071.63  4989.8 1071.46  4990.0 1070.96
  4993.5 1070.96  4993.8 1071.46  4997.5 1072.33  5013.6 1071.82  5041.1 1076.68
  5057.2 1077.87  5062.9 1079.16  5079.0 1079.25  5084.7 1080.72  5095.1 1080.34
  5116.9 1081.91  5122.6 1082.80  5138.7 1083.16  5152.1 1084.82  5176.9 1085.46
#Mann=5,-1,0
  4639.4    0.05       0  4652.0    0.12       0  4704.3    0.05       0
  4989.8    0.05       0  4993.8    0.05       0
Bank Sta=4989.8,4993.8
Exp/Cntr=0.3,0.1

Type RM Length L Ch R = 1,4000,141,141,141
BEGIN DESCRIPTION:
SANFERNANDO066 8.0
END DESCRIPTION:
XS GIS Cut Line= 3
      2805455.68     10251353.14      2805485.07     10250967.16
      2805455.69     10250603.14
#Sta/Elev= 30
  4612.9 1093.02  4623.0 1093.07  4643.0 1090.34  4673.1 1089.07  4713.2 1085.26
  4723.2 1085.59  4733.3 1083.85  4783.4 1081.38  4809.5 1078.37  4823.5 1078.46
  4903.8 1072.58  4965.9 1070.01  4984.0 1069.32  4999.5 1067.39  5014.1 1067.06
  5034.2 1069.32  5074.3 1069.54  5112.4 1064.53  5112.7 1064.03  5116.4 1064.53
  5124.5 1067.72  5164.6 1075.04  5174.2 1075.96  5179.2 1075.24  5189.8 1076.73
  5234.8 1080.71  5244.8 1082.66  5264.9 1084.65  5301.6 1086.76  5365.2 1088.65
#Mann=5,-1,0
  4612.9    0.05       0  4965.9    0.12       0  5112.4    0.07       0
  5116.4    0.12       0  5189.8    0.05       0
Bank Sta=5112.4,5116.4
Exp/Cntr=0.3,0.1

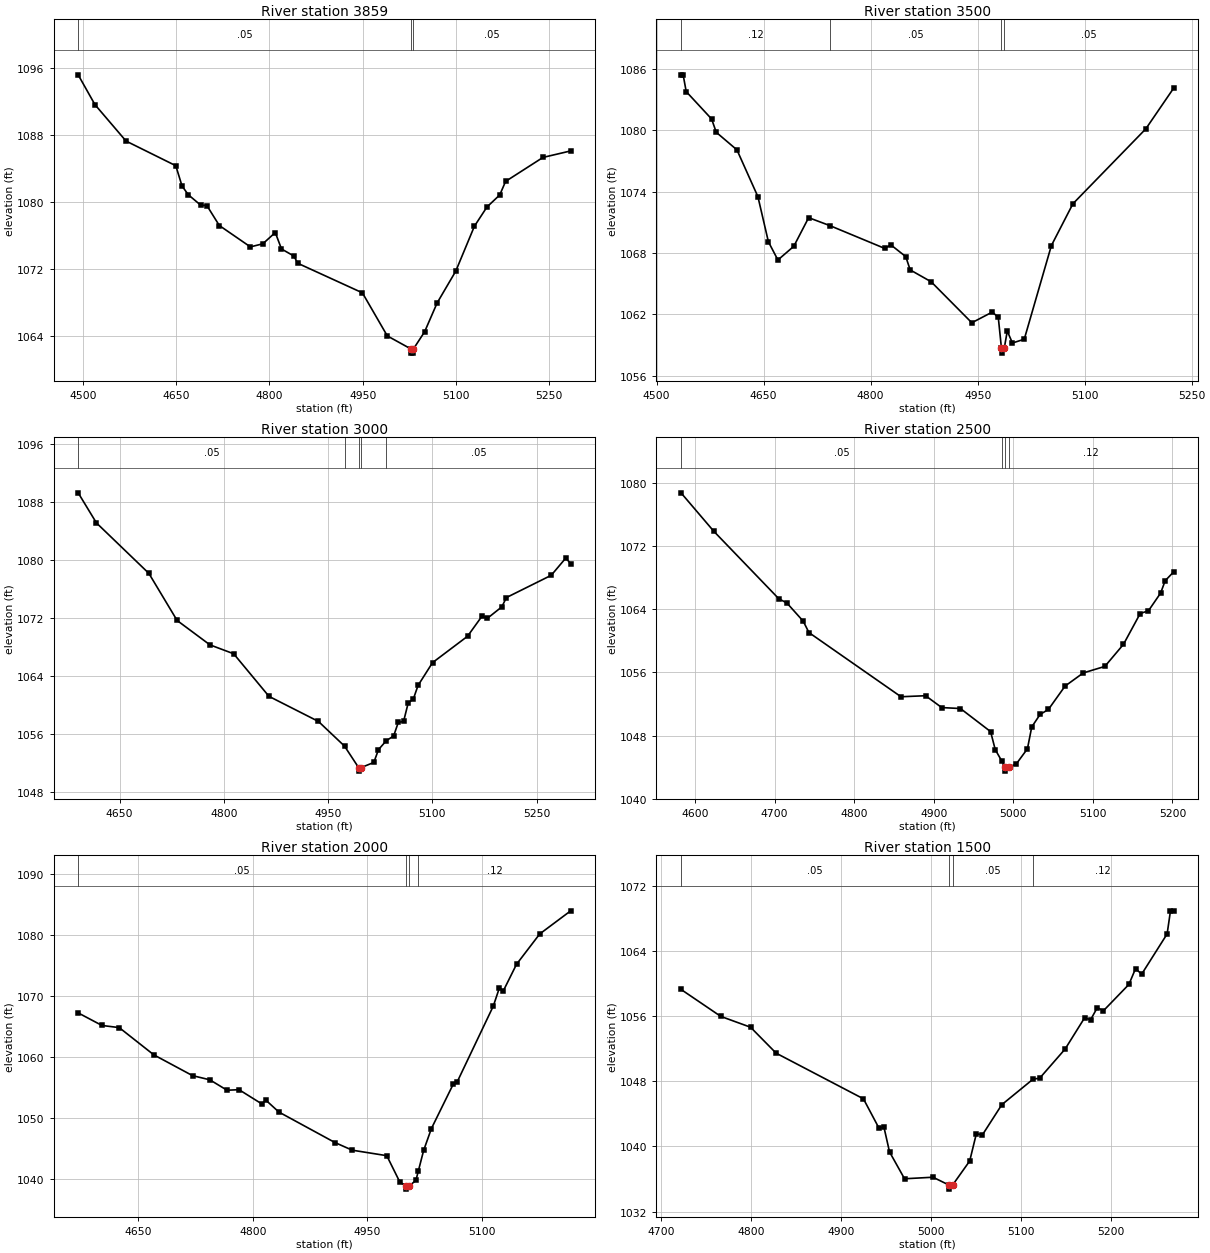
Type RM Length L Ch R = 1,3859,359,359,359
BEGIN DESCRIPTION:
Mapping XS dc1e5549
END DESCRIPTION:
XS GIS Cut Line= 3
      2805615.88     10251410.13      2805615.88     10251056.01
      2805595.05     10250618.52
#Sta/Elev= 30
  4492.5 1095.24  4519.5 1091.67  4569.5 1087.31  4649.5 1084.36  4659.5 1081.94
  4669.5 1080.89  4689.5 1079.64  4699.5 1079.59  4719.5 1077.20  4769.5 1074.64
  4789.5 1075.01  4809.5 1076.36  4819.5 1074.39  4839.5 1073.54  4845.6 1072.68
  4949.6 1069.14  4989.7 1063.98  5027.7 1062.42  5028.0 1061.92  5031.5 1061.92
  5031.7 1062.42  5049.7 1064.48  5069.8 1067.93  5099.8 1071.74  5129.8 1077.12
  5149.9 1079.41  5170.5 1080.86  5179.9 1082.48  5240.0 1085.35  5284.6 1086.13
#Mann=3,-1,0
  4492.5    0.05       0  5027.7    0.05       0  5031.7    0.05       0
Bank Sta=5027.7,5031.7
Exp/Cntr=0.3,0.1

Type RM Length L Ch R = 1,3500,500,500,500
BEGIN DESCRIPTION:
SANFERNANDO066 7.0
END DESCRIPTION:
XS GIS Cut Line= 3
      2806205.66     10251153.08      2805932.18     10250776.01
      2805905.68     10250553.08
#Sta/Elev= 30
  4534.2 1085.42  4537.2 1085.42  4541.5 1083.78  4577.1 1081.10  4583.6 1079.80
  4612.6 1078.08  4642.0 1073.50  4656.7 1069.09  4670.0 1067.31  4692.3 1068.65
  4713.1 1071.45  4742.9 1070.67  4819.8 1068.44  4828.3 1068.79  4849.2 1067.64
  4855.4 1066.34  4884.8 1065.18  4941.8 1061.17  4970.6 1062.22  4978.9 1061.69
  4983.3 1058.70  4983.5 1058.20  4987.3 1058.70  4991.5 1060.36  4998.7 1059.19
  5015.3 1059.56  5053.3 1068.72  5083.5 1072.81  5185.7 1080.14  5224.5 1084.10
#Mann=4,-1,0
  4534.2    0.12       0  4742.9    0.05       0  4983.3    0.05       0
  4987.3    0.05       0
Bank Sta=4983.3,4987.3
Exp/Cntr=0.3,0.1

Type RM Length L Ch R = 1,3000,500,500,500
BEGIN DESCRIPTION:
SANFERNANDO066 6.0
END DESCRIPTION:
XS GIS Cut Line= 3
      2806505.68     10251203.07      2806430.60     10250800.31
      2806205.70     10250603.13
#Sta/Elev= 30
  4590.3 1089.23  4616.6 1085.08  4692.0 1078.13  4732.7 1071.63  4779.9 1068.27
  4814.1 1067.04  4864.9 1061.17  4936.1 1057.71  4973.6 1054.31  4993.8 1051.36
  4994.1 1050.86  4997.8 1051.36  5015.8 1052.06  5022.5 1053.83  5033.8 1055.06
  5044.3 1055.71  5051.0 1057.58  5058.6 1057.71  5065.2 1060.24  5072.8 1060.84
  5079.4 1062.67  5100.3 1065.82  5150.6 1069.45  5171.5 1072.23  5179.1 1071.92
  5200.0 1073.51  5206.6 1074.79  5271.1 1077.86  5292.0 1080.23  5299.1 1079.47
#Mann=5,-1,0
  4590.3    0.05       0  4973.6    0.12       0  4993.8    0.07       0
  4997.8    0.12       0  5033.8    0.05       0
Bank Sta=4993.8,4997.8
Exp/Cntr=0.3,0.1

Type RM Length L Ch R = 1,2500,500,500,500
BEGIN DESCRIPTION:
SANFERNANDO066 5.0
END DESCRIPTION:
XS GIS Cut Line= 3
      2806955.68     10251003.11      2806865.94     10250595.17
      2806805.68     10250403.10
#Sta/Elev= 30
  4582.3 1078.71  4623.3 1073.87  4705.2 1065.31  4715.4 1064.77  4735.9 1062.47
  4743.1 1061.03  4858.8 1052.91  4889.7 1053.04  4910.0 1051.54  4933.5 1051.42
  4971.4 1048.50  4977.2 1046.23  4985.6 1044.75  4989.9 1044.00  4990.1 1043.50
  4993.9 1044.00  5003.7 1044.41  5017.7 1046.33  5023.1 1049.09  5033.6 1050.67
  5044.1 1051.31  5065.0 1054.26  5087.8 1055.92  5115.0 1056.75  5138.4 1059.54
  5159.4 1063.44  5169.8 1063.79  5185.1 1066.03  5190.8 1067.59  5201.3 1068.69
#Mann=4,-1,0
  4582.3    0.05       0  4985.6    0.12       0  4989.9    0.07       0
  4993.9    0.12       0
Bank Sta=4989.9,4993.9
Exp/Cntr=0.3,0.1

Type RM Length L Ch R = 1,2000,500,500,500
BEGIN DESCRIPTION:
SANFERNANDO066 4.0
END DESCRIPTION:
XS GIS Cut Line= 3
      2807155.68     10250853.11      2807341.59     10250466.60
      2807305.68     10250253.10
#Sta/Elev= 30
  4571.1 1067.27  4602.3 1065.21  4624.9 1064.86  4670.2 1060.40  4721.0 1056.99
  4743.6 1056.31  4766.2 1054.60  4781.9 1054.69  4811.5 1052.38  4817.1 1052.97
  4834.1 1051.03  4907.6 1046.03  4930.2 1044.78  4975.5 1043.88  4992.6 1039.56
  5000.7 1038.90  5001.0 1038.40  5004.7 1038.90  5013.7 1039.84  5016.9 1041.39
  5023.8 1044.74  5034.0 1048.33  5062.5 1055.57  5067.6 1055.92  5115.1 1068.39
  5123.1 1071.38  5128.2 1070.87  5145.5 1075.23  5175.9 1080.20  5216.5 1083.99
#Mann=4,-1,0
  4571.1    0.05       0  5000.7    0.05       0  5004.7    0.05       0
  5016.9    0.12       0
Bank Sta=5000.7,5004.7
Exp/Cntr=0.3,0.1

Type RM Length L Ch R = 1,1500,500,500,500
BEGIN DESCRIPTION:
SANFERNANDO066 3.0
END DESCRIPTION:
XS GIS Cut Line= 3
      2807955.70     10250703.14      2807838.33     10250451.46
      2807655.70     10250253.13
#Sta/Elev= 30
  4722.3 1059.26  4766.5 1055.95  4799.6 1054.62  4828.0 1051.44  4925.0 1045.84
  4942.3 1042.24  4947.8 1042.37  4954.0 1039.33  4970.7 1036.03  5002.3 1036.22
  5020.1 1035.26  5020.3 1034.76  5024.1 1035.26  5043.1 1038.21  5050.5 1041.56
  5057.2 1041.41  5078.8 1045.12  5113.6 1048.26  5120.8 1048.36  5149.1 1051.94
  5170.7 1055.76  5177.5 1055.55  5184.9 1057.02  5191.7 1056.64  5220.0 1059.87
  5227.4 1061.81  5234.2 1061.13  5262.5 1066.07  5266.2 1068.90  5269.6 1068.90
#Mann=4,-1,0
  4722.3    0.05       0  5020.1    0.03       0  5024.1    0.05       0
  5113.6    0.12       0
Bank Sta=5020.1,5024.1
Exp/Cntr=0.3,0.1

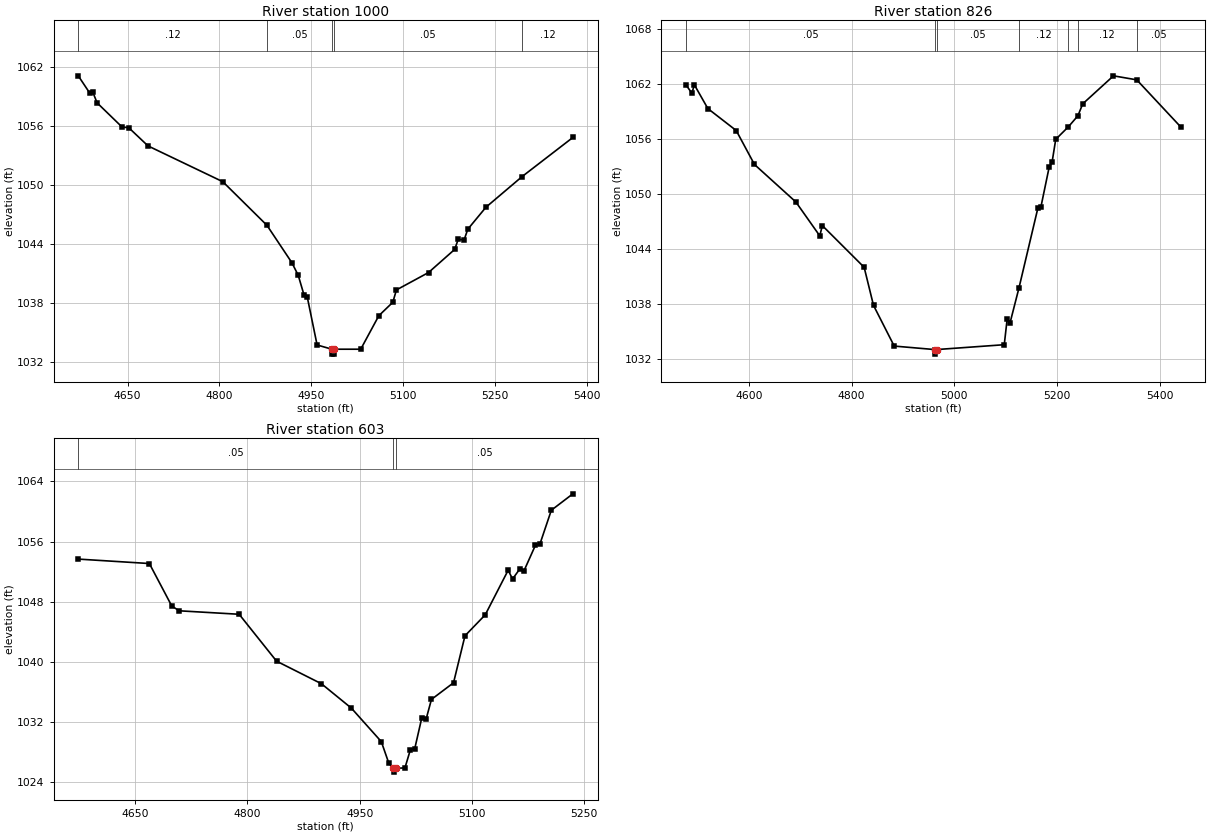
Type RM Length L Ch R = 1,1000,174,174,174
BEGIN DESCRIPTION:
SANFERNANDO066 2.0
END DESCRIPTION:
XS GIS Cut Line= 3
      2808405.69     10250753.14      2808307.65     10250333.85
      2807983.90     10250139.32
#Sta/Elev= 30
  4569.4 1061.11  4588.1 1059.36  4593.2 1059.44  4600.2 1058.36  4641.3 1055.88
  4651.6 1055.85  4683.4 1053.98  4805.6 1050.34  4877.8 1045.90  4918.6 1042.09
  4928.9 1040.81  4938.4 1038.80  4943.5 1038.65  4959.7 1033.73  4984.0 1033.30
  4984.3 1032.80  4987.8 1032.80  4988.0 1033.30  5031.0 1033.30  5060.6 1036.71
  5083.5 1038.08  5089.3 1039.33  5141.8 1041.10  5184.5 1043.45  5190.3 1044.47
  5200.0 1044.42  5205.9 1045.50  5235.6 1047.74  5294.7 1050.86  5377.7 1054.84
#Mann=5,-1,0
  4569.4    0.12       0  4877.8    0.05       0  4984.0    0.03       0
  4988.0    0.05       0  5294.7    0.12       0
Bank Sta=4984,4988
Exp/Cntr=0.3,0.1

Type RM Length L Ch R = 1,826,223,223,223
BEGIN DESCRIPTION:
Mapping XS f7d38f2a
END DESCRIPTION:
XS GIS Cut Line= 4
      2808532.55     10250785.17      2808483.94     10250389.34
      2808456.16     10250174.06      2808290.08     10249869.58
#Sta/Elev= 30
  4477.7 1061.89  4488.9 1061.01  4493.9 1061.91  4520.1 1059.32  4575.3 1056.92
  4610.8 1053.21  4691.4 1049.11  4737.9 1045.41  4742.9 1046.53  4824.3 1041.97
  4842.5 1037.81  4882.8 1033.36  4961.4 1032.98  4961.7 1032.48  4965.4 1032.98
  5097.0 1033.51  5102.7 1036.34  5108.4 1035.93  5125.7 1039.73  5162.5 1048.46
  5168.2 1048.53  5184.3 1052.89  5190.0 1053.44  5197.2 1055.96  5222.0 1057.34
  5240.3 1058.53  5249.8 1059.84  5309.6 1062.90  5354.9 1062.46  5440.4 1057.32
#Mann=7,-1,0
  4477.7    0.05       0  4961.4    0.03       0  4965.4    0.05       0
  5125.7    0.12       0  5222.0    0.05       0  5240.3    0.12       0
  5354.9    0.05       0
Bank Sta=4961.4,4965.4
Exp/Cntr=0.3,0.1

Type RM Length L Ch R = 1,603,0,0,0
BEGIN DESCRIPTION:
SANFERNANDO066 1.0
END DESCRIPTION:
XS GIS Cut Line= 3
      2808680.68     10250628.10      2808680.75     10250202.00
      2808555.71     10250003.15
#Sta/Elev= 30
  4573.9 1053.67  4668.9 1053.08  4698.9 1047.43  4708.9 1046.80  4788.9 1046.34
  4838.9 1040.11  4898.9 1037.11  4938.9 1033.87  4978.9 1029.42  4988.9 1026.56
  4994.9 1025.87  4995.2 1025.37  4998.9 1025.87  5010.5 1025.94  5017.7 1028.33
  5023.6 1028.50  5033.0 1032.59  5038.9 1032.46  5045.9 1035.03  5075.4 1037.24
  5090.7 1043.48  5117.8 1046.27  5148.4 1052.19  5154.3 1051.03  5163.7 1052.32
  5169.6 1052.12  5184.9 1055.52  5190.8 1055.65  5206.1 1060.16  5234.9 1062.34
#Mann=3,-1,0
  4573.9    0.05       0  4994.9    0.05       0  4998.9    0.05       0
Bank Sta=4994.9,4998.9
Exp/Cntr=0.3,0.1

Chan Stop Cuts=-1