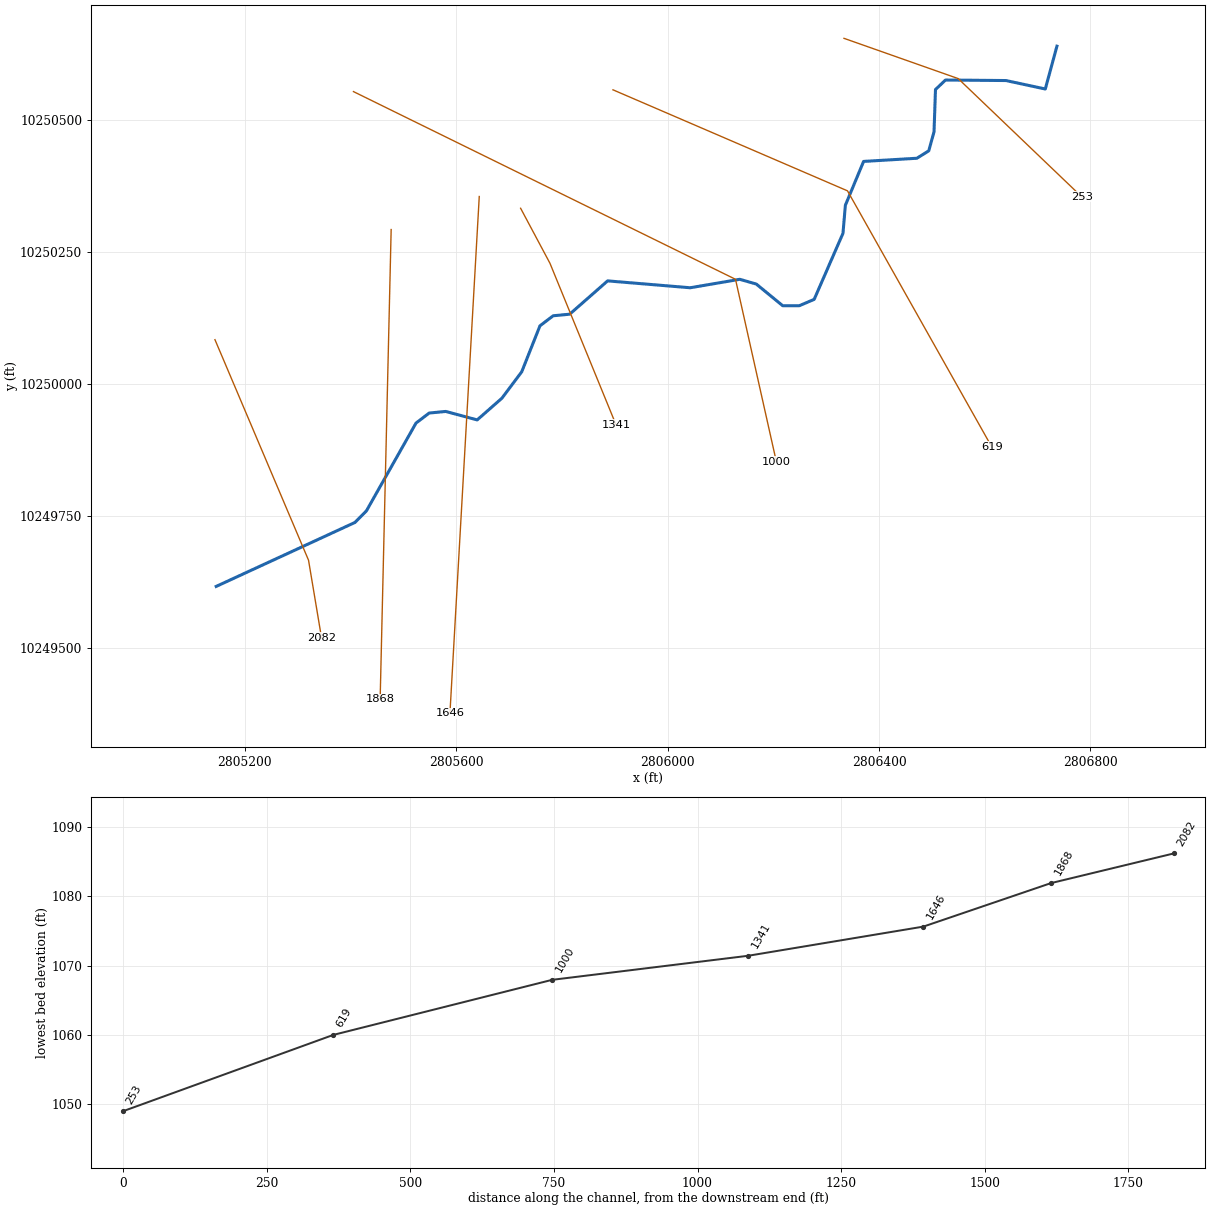
--- SANFERNANDO067.prj (project) ---

Proj Title=SANFERNANDO067 Base Level Engineering
Current Plan=p01
Default Exp/Contr=0.3,0.1
English Units
Geom File=g01
Flow File=f01
Plan File=p01
BEGIN DESCRIPTION:
SANFERNANDO067
END DESCRIPTION:

--- SANFERNANDO067.p01 (plan) ---

Plan Title=Multiple Run
Short Identifier=Multiple
Geom File=g01
Flow File=f01
Subcritical Flow
K Sum by GR= 0
Std Step Tol= 0.01
Critical Tol= 0.01
Num of Std Step Trials= 20
Max Error Tol= 0.3
Flow Tol Ratio= 0.001
Split Flow NTrial= 30
Split Flow Tol= 0.02
Split Flow Ratio= 0.02
Log Output Level= 0
Friction Slope Method= 1
Unsteady Friction Slope Method= 2
Unsteady Bridges Friction Slope Method= 1
Parabolic Critical Depth
Global Vel Dist=  1 , 1 , 1
Global Log Level= 0
CheckData=True
Encroach Param= -1, 0, 0, 0
BEGIN DESCRIPTION:
Multiple Run
END DESCRIPTION:

--- SANFERNANDO067.f01 (steady flow) ---

Flow Title=Multiple
Number of Profiles=7
Profile Names=10-year,25-year,50-year,1pct_min,100-year,1pct_plu,500-year
River Rch & RM= SANFERNANDO067,Reach-1,2082
      79     115     144      90     182     370     256
Boundary for River Rch & Prof#=SANFERNANDO067,Reach-1,1
Up Type=0
Dn Type=3
Dn Slope=0.005
Boundary for River Rch & Prof#=SANFERNANDO067,Reach-1,2
Up Type=0
Dn Type=3
Dn Slope=0.005
Boundary for River Rch & Prof#=SANFERNANDO067,Reach-1,3
Up Type=0
Dn Type=3
Dn Slope=0.005
Boundary for River Rch & Prof#=SANFERNANDO067,Reach-1,4
Up Type=0
Dn Type=3
Dn Slope=0.005
Boundary for River Rch & Prof#=SANFERNANDO067,Reach-1,5
Up Type=0
Dn Type=3
Dn Slope=0.005
Boundary for River Rch & Prof#=SANFERNANDO067,Reach-1,6
Up Type=0
Dn Type=3
Dn Slope=0.005
Boundary for River Rch & Prof#=SANFERNANDO067,Reach-1,7
Up Type=0
Dn Type=3
Dn Slope=0.005

--- SANFERNANDO067.g01 (geometry) ---

Geom Title=Existing Conditions

River Reach=SANFERNANDO067,Reach-1
Reach XY= 30
      2805146.00     10249617.00      2805408.50     10249738.00
      2805430.25     10249760.00      2805524.00     10249926.00
      2805549.00     10249945.00      2805580.25     10249948.00
      2805639.75     10249932.00      2805686.50     10249973.00
      2805724.00     10250023.00      2805758.50     10250110.00
      2805783.50     10250129.00      2805814.75     10250132.00
      2805886.50     10250195.00      2806042.75     10250182.00
      2806136.50     10250198.00      2806167.75     10250189.00
      2806217.75     10250148.00      2806249.00     10250148.00
      2806277.25     10250160.00      2806331.75     10250285.00
      2806336.25     10250338.00      2806370.75     10250421.00
      2806471.50     10250427.00      2806494.00     10250441.00
      2806504.00     10250477.00      2806506.75     10250557.00
      2806525.75     10250575.00      2806640.25     10250574.00
      2806714.50     10250558.00      2806736.50     10250639.00

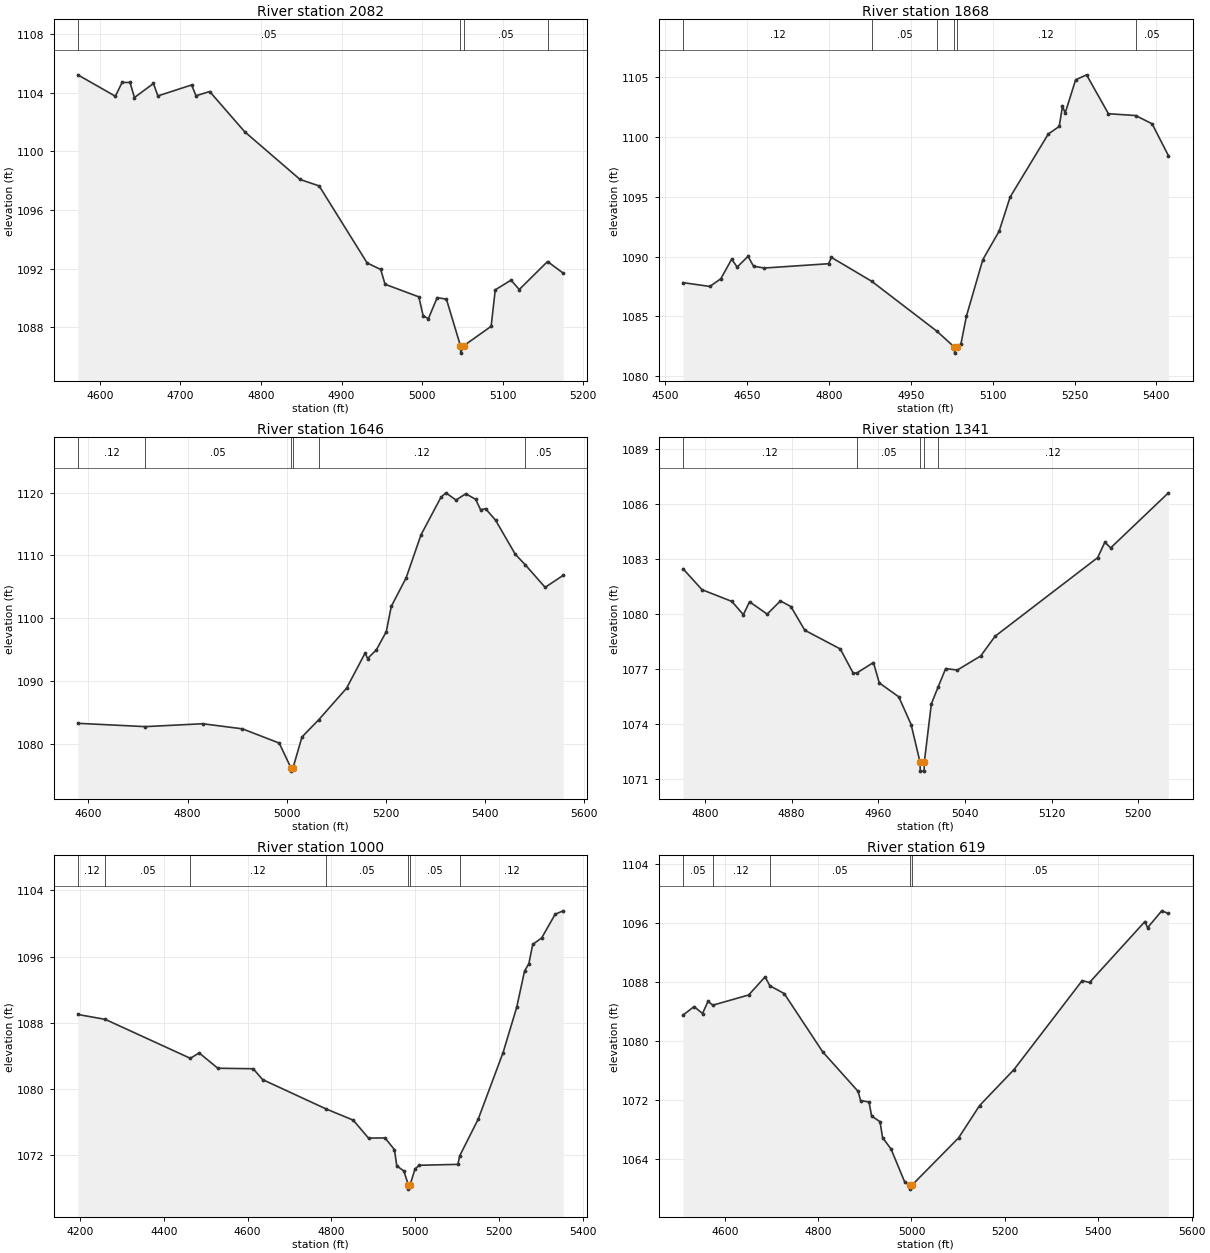
Type RM Length L Ch R = 1,2082,214,214,214
BEGIN DESCRIPTION:
SANFERNANDO067 4.0
END DESCRIPTION:
XS GIS Cut Line= 3
      2805143.66     10250083.79      2805320.71     10249666.46
      2805345.34     10249519.34
#Sta/Elev= 30
  4572.6 1105.22  4619.2 1103.76  4627.6 1104.70  4637.4 1104.70  4642.9 1103.67
  4666.5 1104.63  4672.0 1103.78  4713.9 1104.53  4719.3 1103.79  4736.3 1104.08
  4779.7 1101.34  4848.5 1098.08  4872.2 1097.64  4931.8 1092.38  4948.6 1091.94
  4954.0 1090.93  4995.9 1090.07  5001.3 1088.78  5007.8 1088.58  5018.7 1090.02
  5030.2 1089.91  5047.6 1086.73  5047.9 1086.23  5051.6 1086.73  5085.7 1088.06
  5090.8 1090.55  5110.4 1091.21  5120.6 1090.57  5155.7 1092.48  5175.1 1091.69
#Mann=4,-1,0
  4572.6    0.05       0  5047.6    0.05       0  5051.6    0.05       0
  5155.7    0.12       0
Bank Sta=5047.6,5051.6
Exp/Cntr=0.3,0.1

Type RM Length L Ch R = 1,1868,222,222,222
BEGIN DESCRIPTION:
Mapping XS eb1c55f1
END DESCRIPTION:
XS GIS Cut Line= 2
      2805476.99     10250292.15      2805456.16     10249403.20
#Sta/Elev= 30
  4532.8 1087.82  4581.9 1087.50  4601.9 1088.14  4621.9 1089.78  4631.9 1089.12
  4651.9 1090.02  4661.9 1089.19  4681.9 1089.04  4799.5 1089.40  4804.5 1089.93
  4878.5 1087.93  4997.9 1083.76  5030.0 1082.43  5030.2 1081.93  5034.0 1082.43
  5042.0 1082.72  5052.0 1085.03  5082.0 1089.74  5112.0 1092.13  5132.0 1094.97
  5202.0 1100.24  5222.0 1100.87  5227.9 1102.56  5232.9 1101.99  5252.0 1104.76
  5272.0 1105.18  5312.1 1101.93  5361.9 1101.78  5392.1 1101.09  5422.0 1098.43
#Mann=6,-1,0
  4532.8    0.12       0  4878.5    0.05       0  4997.9    0.12       0
  5030.0    0.07       0  5034.0    0.12       0  5361.9    0.05       0
Bank Sta=5030,5034
Exp/Cntr=0.3,0.1

Type RM Length L Ch R = 1,1646,305,305,305
BEGIN DESCRIPTION:
Mapping XS 3de88847
END DESCRIPTION:
XS GIS Cut Line= 2
      2805643.66     10250354.64      2805588.18     10249376.81
#Sta/Elev= 30
  4578.6 1083.26  4714.8 1082.73  4830.5 1083.19  4910.7 1082.38  4985.0 1080.11
  5008.8 1076.14  5009.1 1075.64  5012.8 1076.14  5030.9 1081.08  5064.8 1083.83
  5121.0 1088.86  5158.4 1094.46  5163.4 1093.58  5181.1 1094.97  5201.1 1097.87
  5211.1 1101.88  5241.2 1106.45  5271.2 1113.30  5311.3 1119.26  5321.3 1119.98
  5341.8 1118.83  5361.4 1119.83  5381.4 1118.95  5391.4 1117.28  5401.4 1117.45
  5421.5 1115.63  5461.5 1110.18  5481.5 1108.52  5521.6 1104.92  5558.0 1106.83
#Mann=6,-1,0
  4578.6    0.12       0  4714.8    0.05       0  5008.8    0.05       0
  5012.8    0.05       0  5064.8    0.12       0  5481.5    0.05       0
Bank Sta=5008.8,5012.8
Exp/Cntr=0.3,0.1

Type RM Length L Ch R = 1,1341,341,341,341
BEGIN DESCRIPTION:
Mapping XS 96e2f733
END DESCRIPTION:
XS GIS Cut Line= 3
      2805721.89     10250332.41      2805777.43     10250228.28
      2805902.44     10249922.68
#Sta/Elev= 30
  4779.7 1082.45  4797.2 1081.31  4824.8 1080.67  4835.4 1079.95  4841.1 1080.65
  4857.4 1079.98  4869.6 1080.70  4879.3 1080.39  4892.1 1079.10  4924.9 1078.08
  4936.9 1076.75  4940.4 1076.78  4955.5 1077.34  4960.9 1076.23  4978.9 1075.47
  4990.3 1073.96  4998.5 1071.92  4998.8 1071.42  5002.3 1071.42  5002.5 1071.92
  5009.0 1075.09  5015.2 1076.00  5022.2 1077.01  5033.0 1076.93  5054.6 1077.70
  5067.8 1078.77  5162.6 1083.06  5169.2 1083.90  5174.6 1083.59  5227.9 1086.59
#Mann=5,-1,0
  4779.7    0.12       0  4940.4    0.05       0  4998.5    0.05       0
  5002.5    0.05       0  5015.2    0.12       0
Bank Sta=4998.5,5002.5
Exp/Cntr=0.3,0.1

Type RM Length L Ch R = 1,1000,381,381,381
BEGIN DESCRIPTION:
SANFERNANDO067 2.0
END DESCRIPTION:
XS GIS Cut Line= 3
      2805405.66     10250553.12      2806128.43     10250198.00
      2806205.68     10249853.14
#Sta/Elev= 30
  4194.7 1089.02  4260.2 1088.43  4463.3 1083.73  4484.4 1084.38  4529.0 1082.53
  4613.4 1082.47  4635.9 1081.16  4787.4 1077.62  4852.1 1076.27  4888.7 1074.10
  4928.1 1074.12  4950.6 1072.71  4956.2 1070.75  4973.1 1070.13  4983.8 1068.44
  4984.0 1067.94  4987.8 1068.44  4999.9 1070.40  5010.2 1070.82  5102.1 1070.93
  5106.4 1071.96  5150.6 1076.39  5210.0 1084.43  5242.4 1089.87  5261.2 1094.26
  5271.5 1095.15  5280.7 1097.47  5302.2 1098.27  5334.3 1101.12  5353.4 1101.53
#Mann=7,-1,0
  4194.7    0.12       0  4260.2    0.05       0  4463.3    0.12       0
  4787.4    0.05       0  4983.8    0.05       0  4987.8    0.05       0
  5106.4    0.12       0
Bank Sta=4983.8,4987.8
Exp/Cntr=0.3,0.1

Type RM Length L Ch R = 1,619,366,366,366
BEGIN DESCRIPTION:
Mapping XS 1820e549
END DESCRIPTION:
XS GIS Cut Line= 3
      2805896.63     10250556.46      2806340.31     10250365.34
      2806613.37     10249880.65
#Sta/Elev= 30
  4510.8 1083.57  4534.4 1084.72  4552.5 1083.78  4564.2 1085.42  4574.6 1084.91
  4651.3 1086.29  4686.5 1088.75  4696.6 1087.55  4727.5 1086.48  4809.6 1078.60
  4885.6 1073.23  4891.0 1071.98  4909.1 1071.78  4914.6 1069.88  4932.6 1069.11
  4938.1 1066.95  4956.2 1065.41  4985.1 1060.99  4996.4 1060.47  4996.7 1059.97
  5000.4 1060.47  5101.0 1066.93  5145.7 1071.29  5219.5 1076.18  5365.4 1088.23
  5381.3 1087.99  5499.9 1096.25  5505.6 1095.41  5535.9 1097.70  5550.2 1097.35
#Mann=5,-1,0
  4510.8    0.05       0  4574.6    0.12       0  4696.6    0.05       0
  4996.4    0.05       0  5000.4    0.05       0
Bank Sta=4996.4,5000.4
Exp/Cntr=0.3,0.1

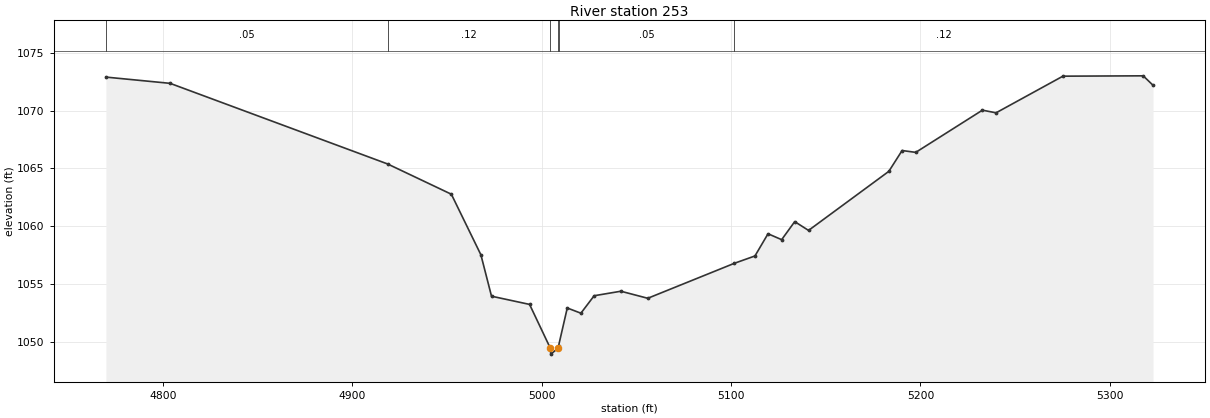
Type RM Length L Ch R = 1,253,0,0,0
BEGIN DESCRIPTION:
SANFERNANDO067 1.0
END DESCRIPTION:
XS GIS Cut Line= 3
      2806333.67     10250653.86      2806549.71     10250577.71
      2806783.69     10250353.84
#Sta/Elev= 30
  4769.9 1072.89  4803.8 1072.35  4918.6 1065.38  4952.3 1062.76  4967.9 1057.52
  4973.5 1053.94  4993.6 1053.23  5004.6 1049.43  5004.8 1048.93  5008.6 1049.43
  5008.9 1049.64  5013.5 1052.92  5020.7 1052.47  5027.7 1053.98  5041.8 1054.37
  5056.0 1053.76  5101.8 1056.79  5112.6 1057.42  5119.5 1059.34  5126.7 1058.83
  5133.6 1060.39  5140.9 1059.63  5183.3 1064.74  5190.3 1066.54  5197.5 1066.38
  5232.7 1070.03  5239.9 1069.80  5275.2 1072.97  5317.6 1073.00  5322.8 1072.18
#Mann=6,-1,0
  4769.9    0.05       0  4918.6    0.12       0  5004.6    0.07       0
  5008.6    0.12       0  5008.9    0.05       0  5101.8    0.12       0
Bank Sta=5004.6,5008.6
Exp/Cntr=0.3,0.1

Chan Stop Cuts=-1