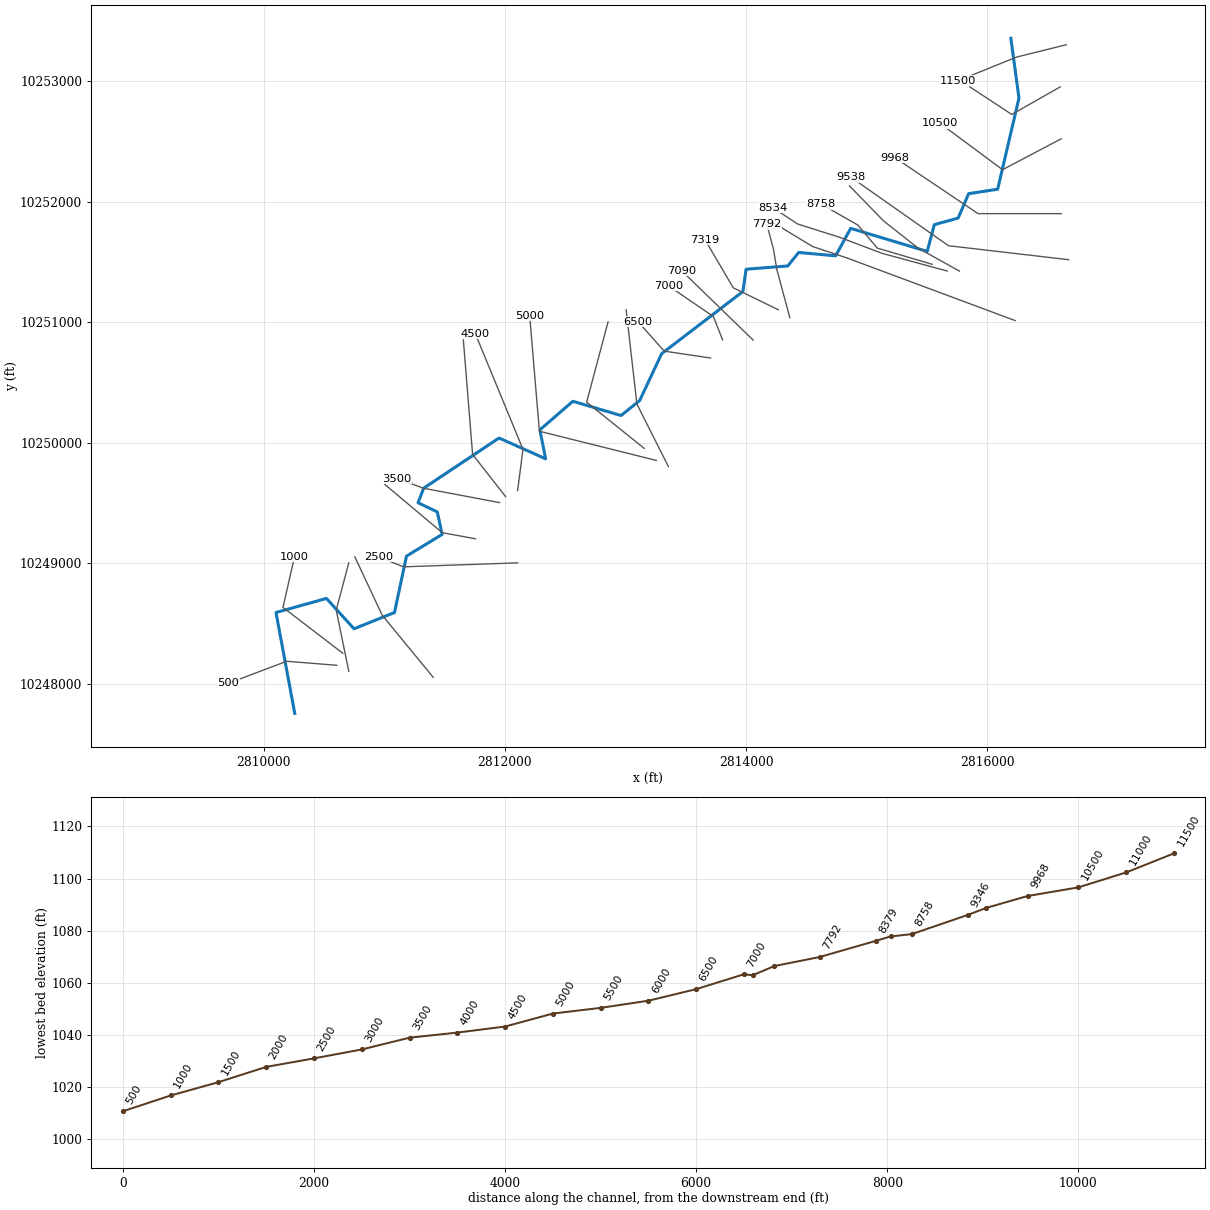
--- SANFERNANDO068.prj (project) ---

Proj Title=SANFERNANDO068 Base Level Engineering
Current Plan=p01
Default Exp/Contr=0.3,0.1
English Units
Geom File=g01
Flow File=f01
Plan File=p01
BEGIN DESCRIPTION:
SANFERNANDO068
END DESCRIPTION:

--- SANFERNANDO068.p01 (plan) ---

Plan Title=Multiple Run
Short Identifier=Multiple
Geom File=g01
Flow File=f01
Subcritical Flow
K Sum by GR= 0
Std Step Tol= 0.01
Critical Tol= 0.01
Num of Std Step Trials= 20
Max Error Tol= 0.3
Flow Tol Ratio= 0.001
Split Flow NTrial= 30
Split Flow Tol= 0.02
Split Flow Ratio= 0.02
Log Output Level= 0
Friction Slope Method= 1
Unsteady Friction Slope Method= 2
Unsteady Bridges Friction Slope Method= 1
Parabolic Critical Depth
Global Vel Dist=  1 , 1 , 1
Global Log Level= 0
CheckData=True
Encroach Param= -1, 0, 0, 0
BEGIN DESCRIPTION:
Multiple Run
END DESCRIPTION:

--- SANFERNANDO068.f01 (steady flow) ---

Flow Title=Multiple
Number of Profiles=7
Profile Names=10-year,25-year,50-year,1pct_min,100-year,1pct_plu,500-year
River Rch & RM= SANFERNANDO068,Reach-1,11500
     466     759     936     542    1239    2829    1687
River Rch & RM= SANFERNANDO068,Reach-1,2000
     521     858    1049     597    1395    3258    1905
Boundary for River Rch & Prof#=SANFERNANDO068,Reach-1,1
Up Type=0
Dn Type=3
Dn Slope=0.005
Boundary for River Rch & Prof#=SANFERNANDO068,Reach-1,2
Up Type=0
Dn Type=3
Dn Slope=0.005
Boundary for River Rch & Prof#=SANFERNANDO068,Reach-1,3
Up Type=0
Dn Type=3
Dn Slope=0.005
Boundary for River Rch & Prof#=SANFERNANDO068,Reach-1,4
Up Type=0
Dn Type=3
Dn Slope=0.005
Boundary for River Rch & Prof#=SANFERNANDO068,Reach-1,5
Up Type=0
Dn Type=3
Dn Slope=0.005
Boundary for River Rch & Prof#=SANFERNANDO068,Reach-1,6
Up Type=0
Dn Type=3
Dn Slope=0.005
Boundary for River Rch & Prof#=SANFERNANDO068,Reach-1,7
Up Type=0
Dn Type=3
Dn Slope=0.005

--- SANFERNANDO068.g01 (geometry) ---

Geom Title=Existing Conditions

River Reach=SANFERNANDO068,Reach-1
Reach XY= 30
      2816196.00     10253356.00      2816263.25     10252860.00
      2816086.50     10252104.00      2815846.00     10252067.00
      2815758.50     10251864.00      2815561.50     10251810.00
      2815502.25     10251588.00      2814867.75     10251779.00
      2814742.75     10251551.00      2814436.50     10251579.00
      2814346.00     10251467.00      2814000.50     10251440.00
      2813974.00     10251255.00      2813300.00     10250739.00
      2813117.75     10250350.00      2812963.25     10250226.00
      2812563.50     10250344.00      2812290.50     10250107.00
      2812337.75     10249867.00      2811951.50     10250039.00
      2811326.75     10249623.00      2811279.75     10249502.00
      2811439.50     10249426.00      2811479.75     10249239.00
      2811184.25     10249059.00      2811084.50     10248591.00
      2810749.25     10248456.00      2810520.25     10248708.00
      2810102.00     10248591.00      2810257.50     10247754.00

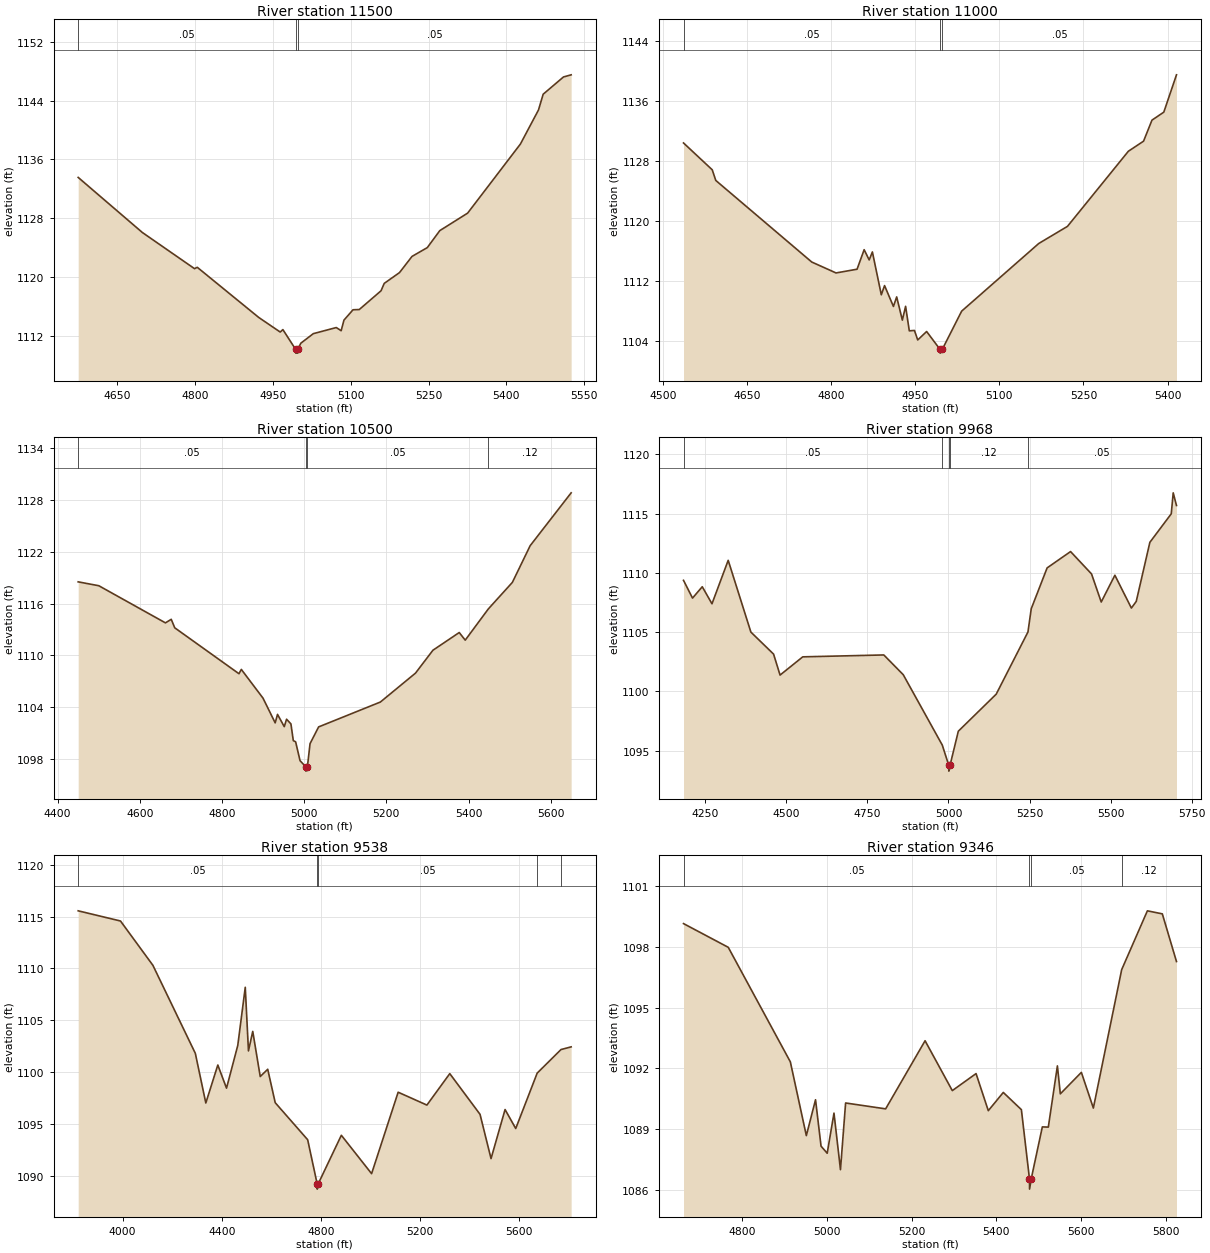
Type RM Length L Ch R = 1,11500,500,500,500
BEGIN DESCRIPTION:
SANFERNANDO068 23.0
END DESCRIPTION:
XS GIS Cut Line= 3
      2816655.67     10253303.11      2816242.50     10253200.17
      2815755.67     10253003.11
#Sta/Elev= 30
  4574.2 1133.56  4697.9 1126.07  4798.7 1121.14  4803.9 1121.33  4922.6 1114.50
  4963.9 1112.52  4969.1 1112.85  4993.8 1110.15  4994.0 1109.65  4997.5 1109.65
  4997.8 1110.15  5003.7 1111.00  5027.8 1112.30  5072.1 1113.13  5081.5 1112.70
  5086.9 1114.14  5104.4 1115.55  5116.4 1115.58  5158.4 1118.13  5164.6 1119.14
  5194.1 1120.61  5218.2 1122.81  5247.7 1124.01  5271.8 1126.32  5325.5 1128.70
  5427.3 1138.10  5462.2 1142.74  5471.2 1144.88  5510.4 1147.23  5525.2 1147.52
#Mann=3,-1,0
  4574.2    0.05       0  4993.8    0.03       0  4997.8    0.05       0
Bank Sta=4993.8,4997.8
Exp/Cntr=0.3,0.1

Type RM Length L Ch R = 1,11000,500,500,500
BEGIN DESCRIPTION:
SANFERNANDO068 22.0
END DESCRIPTION:
XS GIS Cut Line= 3
      2816605.71     10252953.13      2816203.19     10252724.55
      2815855.71     10252953.10
#Sta/Elev= 30
  4537.1 1130.43  4588.3 1126.84  4594.6 1125.42  4765.7 1114.51  4809.0 1113.05
  4846.5 1113.55  4859.1 1116.16  4868.1 1114.79  4873.8 1115.86  4889.7 1110.13
  4895.5 1111.36  4911.3 1108.57  4917.1 1109.85  4927.2 1106.74  4933.0 1108.59
  4939.6 1105.31  4948.8 1105.36  4954.6 1104.09  4970.5 1105.22  4994.4 1102.83
  4994.6 1102.33  4998.4 1102.83  5032.9 1107.94  5170.4 1116.99  5221.6 1119.28
  5330.1 1129.32  5357.2 1130.67  5372.2 1133.48  5393.3 1134.55  5415.9 1139.54
#Mann=3,-1,0
  4537.1    0.05       0  4994.4    0.03       0  4998.4    0.05       0
Bank Sta=4994.4,4998.4
Exp/Cntr=0.3,0.1

Type RM Length L Ch R = 1,10500,532,532,532
BEGIN DESCRIPTION:
SANFERNANDO068 21.0
END DESCRIPTION:
XS GIS Cut Line= 3
      2816613.48     10252522.35      2816127.18     10252265.86
      2815605.65     10252653.14
#Sta/Elev= 30
  4450.2 1118.51  4500.4 1118.06  4662.5 1113.76  4676.6 1114.17  4685.1 1113.19
  4841.4 1107.87  4847.1 1108.37  4899.9 1105.04  4929.5 1102.18  4935.2 1103.16
  4951.6 1101.74  4957.2 1102.60  4967.8 1102.06  4973.6 1100.12  4979.2 1099.99
  4990.0 1097.80  5003.9 1097.09  5004.2 1096.59  5007.9 1097.09  5014.3 1099.77
  5035.2 1101.71  5185.4 1104.59  5270.9 1107.94  5313.3 1110.59  5377.3 1112.64
  5391.9 1111.76  5448.2 1115.38  5506.6 1118.45  5549.9 1122.70  5649.6 1128.82
#Mann=4,-1,0
  4450.2    0.05       0  5003.9    0.05       0  5007.9    0.05       0
  5448.2    0.12       0
Bank Sta=5003.9,5007.9
Exp/Cntr=0.3,0.1

Type RM Length L Ch R = 1,9968,430,430,430
BEGIN DESCRIPTION:
Mapping XS bf16ec33
END DESCRIPTION:
XS GIS Cut Line= 3
      2816613.49     10251901.20      2815924.09     10251901.20
      2815234.68     10252365.36
#Sta/Elev= 30
  4182.8 1109.37  4210.6 1107.87  4240.6 1108.83  4270.6 1107.39  4320.6 1111.06
  4390.6 1105.00  4460.6 1103.14  4480.6 1101.37  4550.6 1102.91  4800.6 1103.07
  4860.6 1101.40  4980.9 1095.46  5000.9 1093.76  5001.1 1093.26  5004.9 1093.76
  5030.4 1096.63  5147.3 1099.76  5245.2 1105.01  5255.3 1106.97  5304.3 1110.42
  5376.6 1111.80  5441.3 1109.91  5471.2 1107.54  5513.3 1109.80  5564.2 1107.03
  5579.2 1107.59  5621.2 1112.58  5687.2 1114.99  5693.2 1116.76  5703.3 1115.69
#Mann=5,-1,0
  4182.8    0.05       0  4980.9    0.12       0  5000.9    0.07       0
  5004.9    0.12       0  5245.2    0.05       0
Bank Sta=5000.9,5004.9
Exp/Cntr=0.3,0.1

Type RM Length L Ch R = 1,9538,192,192,192
BEGIN DESCRIPTION:
Mapping XS 3527c74b
END DESCRIPTION:
XS GIS Cut Line= 3
      2816674.98     10251518.94      2815678.36     10251634.99
      2814872.90     10252201.53
#Sta/Elev= 30
  3821.2 1115.55  3991.8 1114.57  4122.5 1110.30  4293.7 1101.81  4335.9 1097.03
  4384.3 1100.69  4419.4 1098.46  4464.8 1102.58  4495.0 1108.18  4507.9 1102.05
  4525.2 1103.93  4555.4 1099.58  4585.6 1100.28  4615.8 1097.06  4746.7 1093.49
  4785.0 1089.23  4785.2 1088.73  4789.0 1089.23  4882.5 1093.92  5004.5 1090.22
  5111.6 1098.07  5227.5 1096.83  5319.8 1099.86  5441.8 1095.94  5486.2 1091.67
  5542.8 1096.40  5585.8 1094.57  5672.3 1099.91  5768.3 1102.18  5809.3 1102.44
#Mann=5,-1,0
  3821.2    0.05       0  4785.0    0.03       0  4789.0    0.05       0
  5672.3    0.12       0  5768.3    0.05       0
Bank Sta=4785,4789
Exp/Cntr=0.3,0.1

Type RM Length L Ch R = 1,9346,588,588,588
BEGIN DESCRIPTION:
Mapping XS 14c9d1e1
END DESCRIPTION:
XS GIS Cut Line= 4
      2815769.01     10251424.61      2815426.10     10251615.60
      2815139.64     10251841.30      2814857.50     10252132.12
#Sta/Elev= 30
  4662.3 1099.14  4767.8 1097.97  4914.2 1092.32  4951.9 1088.68  4973.6 1090.45
  4986.6 1088.16  5001.1 1087.81  5017.1 1089.79  5032.4 1087.00  5044.5 1090.29
  5138.9 1090.00  5231.9 1093.36  5296.1 1090.90  5352.1 1091.74  5381.0 1089.91
  5416.3 1090.81  5459.0 1089.96  5478.1 1086.54  5478.3 1086.04  5482.1 1086.54
  5508.4 1089.11  5522.5 1089.10  5543.9 1092.12  5550.8 1090.74  5600.4 1091.80
  5628.7 1090.04  5695.5 1096.87  5756.1 1099.77  5791.3 1099.62  5824.7 1097.27
#Mann=4,-1,0
  4662.3    0.05       0  5478.1    0.05       0  5482.1    0.05       0
  5695.5    0.12       0
Bank Sta=5478.1,5482.1
Exp/Cntr=0.3,0.1

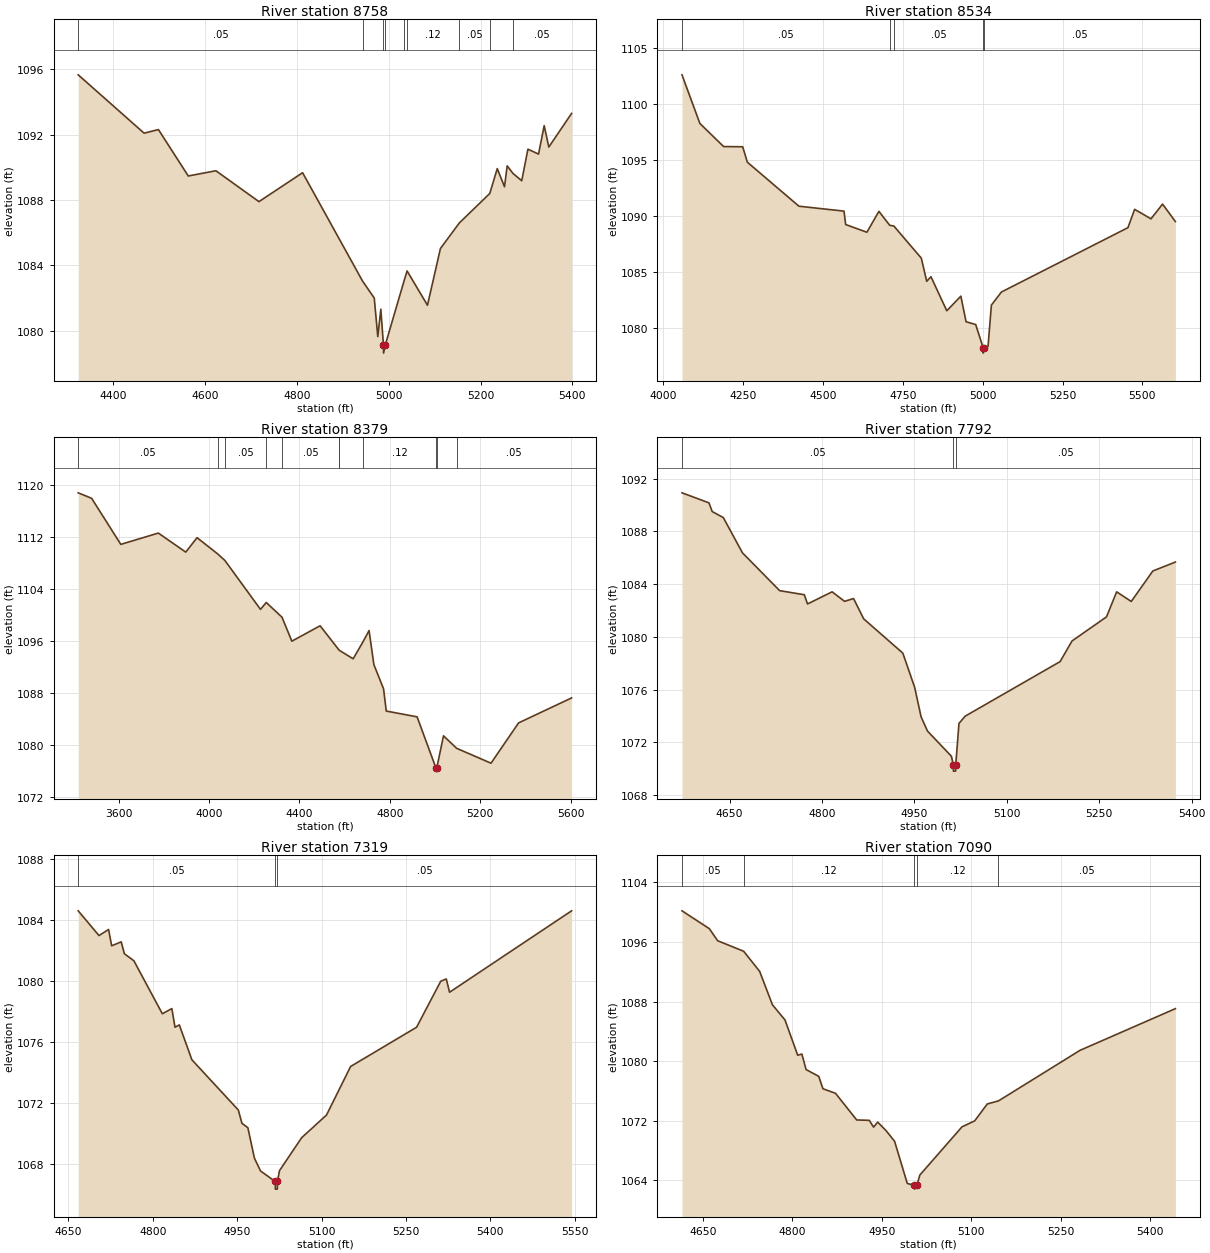
Type RM Length L Ch R = 1,8758,224,224,224
BEGIN DESCRIPTION:
Mapping XS be9828c1
END DESCRIPTION:
XS GIS Cut Line= 4
      2815543.27     10251481.06      2815087.55     10251615.60
      2814926.96     10251806.57      2814623.15     10251980.18
#Sta/Elev= 30
  4323.6 1095.66  4467.1 1092.09  4498.3 1092.31  4563.3 1089.47  4623.5 1089.79
  4717.3 1087.90  4812.3 1089.67  4942.9 1083.04  4968.4 1082.00  4976.1 1079.64
  4982.7 1081.32  4988.4 1079.13  4988.7 1078.63  4992.4 1079.13  5032.8 1083.00
  5039.9 1083.66  5084.3 1081.56  5112.5 1085.03  5153.8 1086.60  5220.0 1088.40
  5236.3 1089.92  5252.1 1088.81  5257.9 1090.09  5270.4 1089.63  5289.6 1089.18
  5303.1 1091.11  5326.2 1090.81  5338.5 1092.55  5348.6 1091.24  5398.2 1093.30
#Mann=9,-1,0
  4323.6    0.05       0  4942.9    0.12       0  4988.4    0.07       0
  4992.4    0.12       0  5032.8    0.05       0  5039.9    0.12       0
  5153.8    0.05       0  5220.0    0.12       0  5270.4    0.05       0
Bank Sta=4988.4,4992.4
Exp/Cntr=0.3,0.1

Type RM Length L Ch R = 1,8534,155,155,155
BEGIN DESCRIPTION:
Mapping XS 4ad7ec33
END DESCRIPTION:
XS GIS Cut Line= 5
      2815669.14     10251424.63      2815126.62     10251572.20
      2814770.71     10251706.75      2814427.83     10251815.25
      2814225.12     10251948.96
#Sta/Elev= 30
  4058.1 1102.63  4114.1 1098.28  4188.4 1096.21  4248.2 1096.19  4262.8 1094.81
  4424.4 1090.87  4565.5 1090.43  4570.7 1089.23  4637.2 1088.54  4674.8 1090.41
  4708.7 1089.16  4721.5 1089.10  4807.6 1086.22  4824.5 1084.15  4837.8 1084.56
  4887.4 1081.51  4931.4 1082.82  4947.8 1080.53  4977.9 1080.28  5001.1 1078.22
  5001.3 1077.72  5005.1 1078.22  5016.6 1078.34  5027.1 1082.02  5058.5 1083.19
  5454.7 1088.95  5475.7 1090.59  5526.9 1089.74  5563.1 1091.06  5603.3 1089.50
#Mann=5,-1,0
  4058.1    0.05       0  4708.7    0.12       0  4721.5    0.05       0
  5001.1    0.05       0  5005.1    0.05       0
Bank Sta=5001.1,5005.1
Exp/Cntr=0.3,0.1

Type RM Length L Ch R = 1,8379,587,587,587
BEGIN DESCRIPTION:
Mapping XS af6e62e0
END DESCRIPTION:
XS GIS Cut Line= 4
      2816231.24     10251013.82      2814838.75     10251532.59
      2814552.06     10251628.16      2814215.14     10251832.63
#Sta/Elev= 30
  3421.7 1118.83  3481.0 1117.99  3610.1 1110.90  3776.1 1112.64  3897.4 1109.71
  3947.4 1111.93  4039.1 1109.42  4070.6 1108.42  4228.0 1100.90  4253.3 1101.96
  4323.0 1099.70  4366.7 1096.01  4491.6 1098.38  4574.8 1094.67  4575.3 1094.63
  4637.9 1093.30  4681.8 1095.94  4708.2 1097.64  4729.5 1092.41  4772.2 1088.69
  4784.3 1085.26  4920.7 1084.37  5003.8 1076.52  5004.0 1076.02  5007.8 1076.52
  5037.4 1081.45  5095.6 1079.53  5247.5 1077.24  5369.6 1083.44  5604.0 1087.28
#Mann=11,-1,0
  3421.7    0.05       0  4039.1    0.12       0  4070.6    0.05       0
  4253.3    0.12       0  4323.0    0.05       0  4574.8    0.12       0
  4575.3    0.05       0  4681.8    0.12       0  5003.8    0.07       0
  5007.8    0.12       0  5095.6    0.05       0
Bank Sta=5003.8,5007.8
Exp/Cntr=0.3,0.1

Type RM Length L Ch R = 1,7792,473,473,473
BEGIN DESCRIPTION:
Mapping XS 22dd36fa
END DESCRIPTION:
XS GIS Cut Line= 4
      2814362.73     10251038.35      2814254.22     10251441.99
      2814228.18     10251602.58      2814171.75     10251815.26
#Sta/Elev= 30
  4572.9 1090.92  4616.7 1090.16  4621.9 1089.50  4640.0 1089.04  4671.0 1086.37
  4731.4 1083.50  4771.4 1083.19  4776.6 1082.49  4816.5 1083.41  4836.7 1082.69
  4851.3 1082.90  4867.8 1081.36  4931.3 1078.76  4950.6 1076.15  4960.9 1073.93
  4971.3 1072.85  5010.1 1070.94  5013.2 1070.31  5013.4 1069.81  5016.9 1069.81
  5017.2 1070.31  5022.4 1073.43  5032.5 1073.98  5186.6 1078.12  5205.8 1079.68
  5261.8 1081.51  5278.3 1083.41  5302.0 1082.68  5337.0 1084.99  5373.6 1085.67
#Mann=3,-1,0
  4572.9    0.05       0  5013.2    0.05       0  5017.2    0.05       0
Bank Sta=5013.2,5017.2
Exp/Cntr=0.3,0.1

Type RM Length L Ch R = 1,7319,229,229,229
BEGIN DESCRIPTION:
Mapping XS bb5385ef
END DESCRIPTION:
XS GIS Cut Line= 4
      2814267.23     10251103.45      2814071.93     10251198.93
      2813893.98     10251285.74      2813660.16     10251684.10
#Sta/Elev= 30
  4667.3 1084.58  4704.3 1082.96  4721.3 1083.36  4726.8 1082.29  4743.8 1082.55
  4749.4 1081.77  4766.3 1081.31  4816.9 1077.84  4833.8 1078.18  4839.4 1076.96
  4847.1 1077.11  4869.4 1074.83  4952.0 1071.54  4958.4 1070.67  4969.0 1070.38
  4980.6 1068.39  4991.5 1067.55  5017.6 1066.86  5017.9 1066.36  5021.4 1066.36
  5021.6 1066.86  5025.2 1067.57  5064.7 1069.73  5108.8 1071.21  5151.7 1074.39
  5269.0 1076.96  5311.9 1079.97  5321.8 1080.12  5327.6 1079.25  5544.6 1084.58
#Mann=3,-1,0
  4667.3    0.05       0  5017.6    0.03       0  5021.6    0.05       0
Bank Sta=5017.6,5021.6
Exp/Cntr=0.3,0.1

Type RM Length L Ch R = 1,7090,90,90,90
BEGIN DESCRIPTION:
Mapping XS 51816401
END DESCRIPTION:
XS GIS Cut Line= 2
      2814058.88     10250851.74      2813464.72     10251428.56
#Sta/Elev= 30
  4614.6 1100.18  4660.4 1097.79  4674.5 1096.16  4718.1 1094.75  4745.0 1092.04
  4766.4 1087.56  4787.5 1085.52  4808.8 1080.79  4815.8 1080.94  4822.9 1078.86
  4844.1 1077.95  4851.2 1076.28  4872.3 1075.67  4907.8 1072.09  4928.9 1072.04
  4936.1 1071.13  4943.1 1071.80  4957.2 1070.65  4971.4 1069.23  4992.7 1063.57
  5004.8 1063.30  5005.1 1062.80  5008.8 1063.30  5013.8 1064.69  5084.6 1071.17
  5105.9 1071.97  5127.0 1074.24  5145.8 1074.65  5282.6 1081.44  5442.7 1087.04
#Mann=5,-1,0
  4614.6    0.05       0  4718.1    0.12       0  5004.8    0.07       0
  5008.8    0.12       0  5145.8    0.05       0
Bank Sta=5004.8,5008.8
Exp/Cntr=0.3,0.1

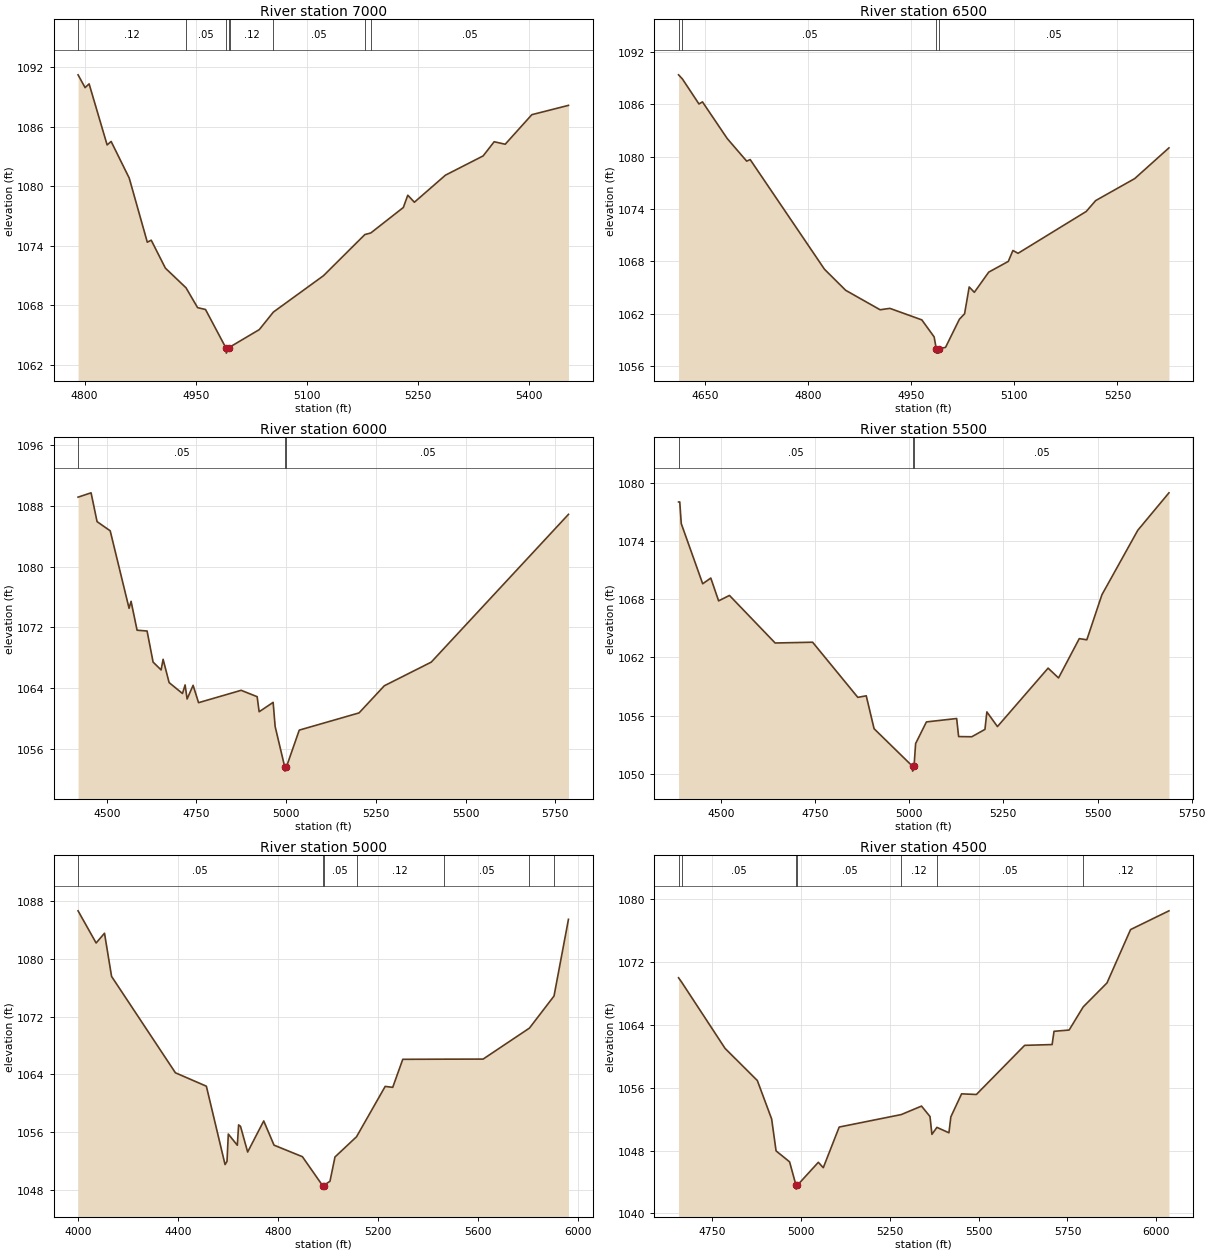
Type RM Length L Ch R = 1,7000,500,500,500
BEGIN DESCRIPTION:
SANFERNANDO068 14.0
END DESCRIPTION:
XS GIS Cut Line= 3
      2813805.68     10250853.13      2813729.12     10251047.28
      2813355.65     10251303.13
#Sta/Elev= 30
  4791.3 1091.26  4800.8 1089.97  4806.2 1090.35  4830.5 1084.19  4835.9 1084.54
  4860.3 1080.85  4884.7 1074.38  4890.0 1074.58  4909.1 1071.76  4936.9 1069.78
  4952.5 1067.78  4963.2 1067.59  4990.9 1063.69  4991.2 1063.19  4994.9 1063.69
  4995.7 1063.79  5035.7 1065.56  5054.7 1067.33  5122.3 1071.00  5178.1 1075.15
  5186.1 1075.31  5230.0 1077.88  5236.0 1079.12  5244.9 1078.41  5286.8 1081.14
  5337.6 1083.08  5352.5 1084.51  5367.4 1084.26  5403.3 1087.24  5452.7 1088.18
#Mann=8,-1,0
  4791.3    0.12       0  4936.9    0.05       0  4990.9    0.07       0
  4994.9    0.05       0  4995.7    0.12       0  5054.7    0.05       0
  5178.1    0.12       0  5186.1    0.05       0
Bank Sta=4990.9,4994.9
Exp/Cntr=0.3,0.1

Type RM Length L Ch R = 1,6500,500,500,500
BEGIN DESCRIPTION:
SANFERNANDO068 13.0
END DESCRIPTION:
XS GIS Cut Line= 3
      2813705.72     10250703.11      2813321.53     10250760.14
      2813105.68     10251003.11
#Sta/Elev= 30
  4611.6 1089.36  4617.2 1088.89  4641.3 1086.02  4646.4 1086.26  4682.4 1082.06
  4710.7 1079.47  4715.8 1079.65  4823.9 1067.08  4854.7 1064.67  4904.8 1062.44
  4919.0 1062.60  4965.5 1061.28  4983.4 1059.33  4986.5 1057.97  4986.7 1057.47
  4990.2 1057.47  4990.5 1057.97  5000.0 1058.13  5020.2 1061.36  5027.7 1061.98
  5034.4 1065.05  5041.9 1064.44  5062.8 1066.75  5091.3 1067.98  5098.0 1069.23
  5105.5 1068.91  5204.6 1073.70  5218.4 1074.95  5275.2 1077.47  5325.0 1080.99
#Mann=4,-1,0
  4611.6    0.12       0  4617.2    0.05       0  4986.5    0.05       0
  4990.5    0.05       0
Bank Sta=4986.5,4990.5
Exp/Cntr=0.3,0.1

Type RM Length L Ch R = 1,6000,500,500,500
BEGIN DESCRIPTION:
SANFERNANDO068 12.0
END DESCRIPTION:
XS GIS Cut Line= 3
      2813355.68     10249803.12      2813094.75     10250321.23
      2813005.69     10251103.07
#Sta/Elev= 30
  4419.9 1089.16  4456.2 1089.73  4472.9 1085.93  4509.5 1084.72  4562.1 1074.50
  4567.7 1075.42  4584.4 1071.61  4612.3 1071.50  4629.1 1067.40  4651.4 1066.37
  4657.0 1067.77  4673.7 1064.70  4711.0 1063.26  4718.3 1064.39  4723.9 1062.54
  4740.6 1064.34  4755.8 1062.05  4874.5 1063.68  4919.1 1062.84  4924.7 1060.85
  4963.7 1062.09  4969.3 1058.90  4996.3 1053.52  4996.5 1053.02  5000.3 1053.52
  5036.5 1058.43  5203.2 1060.70  5273.6 1064.28  5404.5 1067.40  5786.9 1086.89
#Mann=3,-1,0
  4419.9    0.05       0  4996.3    0.05       0  5000.3    0.05       0
Bank Sta=4996.3,5000.3
Exp/Cntr=0.3,0.1

Type RM Length L Ch R = 1,5500,500,500,500
BEGIN DESCRIPTION:
SANFERNANDO068 11.0
END DESCRIPTION:
XS GIS Cut Line= 3
      2813155.68     10249953.11      2812678.17     10250336.70
      2812855.70     10251003.16
#Sta/Elev= 30
  4387.5 1078.00  4390.7 1078.00  4394.7 1075.77  4451.6 1069.57  4473.1 1070.16
  4493.9 1067.81  4522.7 1068.37  4644.0 1063.47  4743.5 1063.55  4863.5 1057.87
  4885.9 1058.03  4906.7 1054.64  5008.8 1050.77  5009.0 1050.27  5012.8 1050.77
  5017.0 1053.11  5045.7 1055.34  5126.0 1055.69  5131.2 1053.83  5166.1 1053.81
  5201.1 1054.57  5206.2 1056.37  5234.3 1054.86  5368.8 1060.88  5396.5 1059.87
  5451.6 1063.92  5471.6 1063.80  5511.7 1068.44  5606.9 1075.08  5689.7 1078.94
#Mann=3,-1,0
  4387.5    0.05       0  5008.8    0.03       0  5012.8    0.05       0
Bank Sta=5008.8,5012.8
Exp/Cntr=0.3,0.1

Type RM Length L Ch R = 1,5000,500,500,500
BEGIN DESCRIPTION:
SANFERNANDO068 10.0
END DESCRIPTION:
XS GIS Cut Line= 3
      2813255.73     10249853.10      2812286.35     10250095.38
      2812205.69     10251053.08
#Sta/Elev= 30
  4000.8 1086.69  4073.0 1082.23  4106.5 1083.58  4134.8 1077.59  4390.0 1064.22
  4513.7 1062.36  4588.4 1051.49  4596.2 1051.93  4601.4 1055.72  4637.4 1054.17
  4642.6 1056.99  4650.2 1056.79  4678.7 1053.23  4743.0 1057.54  4784.2 1054.18
  4897.6 1052.58  4978.1 1048.58  4978.3 1048.08  4982.1 1048.58  5007.8 1049.17
  5027.8 1052.54  5114.0 1055.35  5228.5 1062.33  5258.6 1062.20  5298.8 1066.09
  5464.1 1066.11  5619.9 1066.12  5805.1 1070.42  5903.4 1074.87  5961.1 1085.51
#Mann=7,-1,0
  4000.8    0.05       0  4978.1    0.05       0  4982.1    0.05       0
  5114.0    0.12       0  5464.1    0.05       0  5805.1    0.12       0
  5903.4    0.05       0
Bank Sta=4978.1,4982.1
Exp/Cntr=0.3,0.1

Type RM Length L Ch R = 1,4500,500,500,500
BEGIN DESCRIPTION:
SANFERNANDO068 9.0
END DESCRIPTION:
XS GIS Cut Line= 3
      2812105.69     10249603.15      2812150.08     10249945.28
      2811755.70     10250903.07
#Sta/Elev= 30
  4655.0 1070.02  4663.9 1069.45  4786.0 1061.02  4876.8 1056.93  4917.1 1052.03
  4929.6 1047.96  4967.6 1046.57  4985.7 1043.59  4986.0 1043.09  4989.7 1043.59
  5048.6 1046.51  5062.5 1045.82  5107.3 1051.00  5282.1 1052.59  5339.1 1053.67
  5363.0 1052.34  5368.4 1050.07  5382.5 1050.96  5416.3 1050.27  5421.7 1052.30
  5451.9 1055.23  5493.6 1055.15  5629.5 1061.41  5706.8 1061.51  5712.2 1063.20
  5754.7 1063.36  5794.4 1066.31  5861.3 1069.36  5927.7 1076.16  6035.8 1078.55
#Mann=7,-1,0
  4655.0    0.12       0  4663.9    0.05       0  4985.7    0.05       0
  4989.7    0.05       0  5282.1    0.12       0  5382.5    0.05       0
  5794.4    0.12       0
Bank Sta=4985.7,4989.7
Exp/Cntr=0.3,0.1

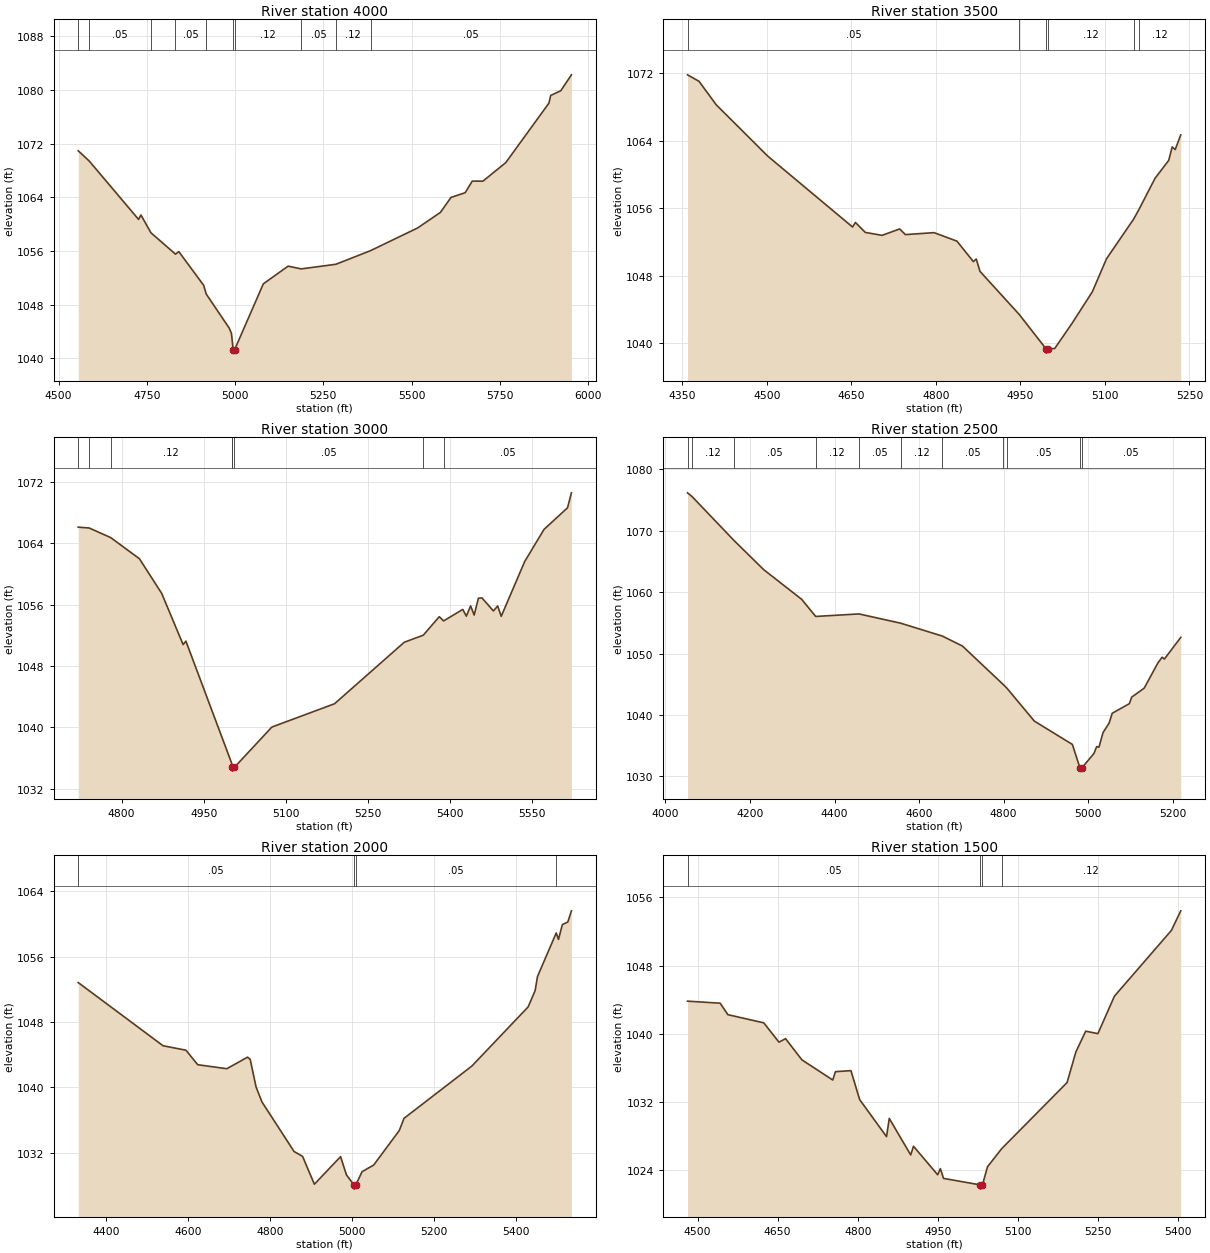
Type RM Length L Ch R = 1,4000,500,500,500
BEGIN DESCRIPTION:
SANFERNANDO068 8.0
END DESCRIPTION:
XS GIS Cut Line= 3
      2812005.71     10249553.07      2811732.30     10249903.28
      2811655.69     10250853.10
#Sta/Elev= 30
  4555.7 1070.95  4586.9 1069.42  4726.7 1060.71  4733.4 1061.37  4761.7 1058.72
  4831.3 1055.53  4840.7 1055.91  4911.2 1050.88  4918.3 1049.59  4983.6 1044.49
  4989.9 1043.70  4994.7 1041.27  4995.0 1040.77  4998.7 1041.27  5080.1 1051.10
  5150.3 1053.74  5187.5 1053.33  5285.7 1054.02  5383.9 1056.05  5517.0 1059.43
  5581.7 1061.75  5611.8 1063.99  5651.9 1064.69  5672.0 1066.42  5702.1 1066.41
  5766.8 1069.17  5889.2 1078.05  5894.2 1079.19  5922.8 1079.90  5952.9 1082.27
#Mann=10,-1,0
  4555.7    0.12       0  4586.9    0.05       0  4761.7    0.12       0
  4831.3    0.05       0  4918.3    0.12       0  4994.7    0.07       0
  4998.7    0.12       0  5187.5    0.05       0  5285.7    0.12       0
  5383.9    0.05       0
Bank Sta=4994.7,4998.7
Exp/Cntr=0.3,0.1

Type RM Length L Ch R = 1,3500,500,500,500
BEGIN DESCRIPTION:
SANFERNANDO068 7.0
END DESCRIPTION:
XS GIS Cut Line= 3
      2811955.69     10249503.11      2811325.96     10249622.26
      2811105.73     10249703.10
#Sta/Elev= 30
  4359.1 1071.82  4379.5 1071.05  4410.0 1068.27  4501.6 1062.17  4652.0 1053.77
  4657.1 1054.31  4674.6 1053.13  4704.4 1052.78  4735.7 1053.54  4745.8 1052.87
  4796.7 1053.10  4837.4 1052.09  4866.5 1049.66  4871.6 1049.98  4878.2 1048.51
  4948.1 1043.38  4995.6 1039.31  4995.8 1038.81  4999.6 1039.31  5010.9 1039.36
  5041.8 1042.36  5077.6 1046.08  5102.8 1050.00  5150.9 1054.70  5160.1 1055.81
  5188.9 1059.54  5213.3 1061.68  5219.4 1063.27  5224.7 1062.95  5234.6 1064.69
#Mann=6,-1,0
  4359.1    0.05       0  4948.1    0.12       0  4995.6    0.07       0
  4999.6    0.12       0  5150.9    0.05       0  5160.1    0.12       0
Bank Sta=4995.6,4999.6
Exp/Cntr=0.3,0.1

Type RM Length L Ch R = 1,3000,500,500,500
BEGIN DESCRIPTION:
SANFERNANDO068 6.0
END DESCRIPTION:
XS GIS Cut Line= 3
      2811755.65     10249203.12      2811481.08     10249253.19
      2811005.71     10249653.09
#Sta/Elev= 30
  4720.9 1066.11  4741.0 1066.00  4780.2 1064.75  4832.7 1061.99  4873.3 1057.47
  4912.4 1050.79  4917.5 1051.24  5000.8 1035.36  5002.1 1034.78  5002.3 1034.28
  5006.1 1034.78  5074.4 1040.03  5188.8 1043.07  5316.2 1051.10  5350.7 1052.01
  5380.0 1054.43  5387.9 1053.88  5422.9 1055.38  5429.4 1054.50  5437.2 1055.84
  5443.7 1054.64  5451.4 1056.84  5457.9 1056.88  5478.8 1055.18  5486.6 1055.82
  5493.1 1054.48  5536.0 1061.64  5571.2 1065.82  5614.1 1068.64  5621.2 1070.59
#Mann=8,-1,0
  4720.9    0.12       0  4741.0    0.05       0  4780.2    0.12       0
  5000.8    0.05       0  5002.1    0.07       0  5006.1    0.05       0
  5350.7    0.12       0  5387.9    0.05       0
Bank Sta=5002.1,5006.1
Exp/Cntr=0.3,0.1

Type RM Length L Ch R = 1,2500,500,500,500
BEGIN DESCRIPTION:
SANFERNANDO068 5.0
END DESCRIPTION:
XS GIS Cut Line= 3
      2812105.67     10249003.11      2811158.55     10248970.13
      2810955.66     10249053.12
#Sta/Elev= 30
  4052.3 1076.19  4063.2 1075.57  4161.9 1068.45  4232.4 1063.68  4322.5 1058.83
  4355.5 1056.05  4457.9 1056.46  4556.6 1054.95  4655.3 1052.85  4702.7 1051.23
  4799.1 1044.97  4807.5 1044.40  4872.8 1039.00  4962.8 1035.20  4980.9 1031.35
  4981.1 1030.85  4984.9 1031.35  5013.9 1033.73  5020.2 1034.84  5025.6 1034.75
  5035.5 1037.15  5049.6 1038.66  5057.1 1040.28  5097.6 1041.84  5103.0 1042.90
  5132.7 1044.37  5165.2 1048.48  5175.1 1049.41  5180.5 1049.11  5219.2 1052.64
#Mann=11,-1,0
  4052.3    0.05       0  4063.2    0.12       0  4161.9    0.05       0
  4355.5    0.12       0  4457.9    0.05       0  4556.6    0.12       0
  4655.3    0.05       0  4799.1    0.12       0  4807.5    0.05       0
  4980.9    0.05       0  4984.9    0.05       0
Bank Sta=4980.9,4984.9
Exp/Cntr=0.3,0.1

Type RM Length L Ch R = 1,2000,500,500,500
BEGIN DESCRIPTION:
SANFERNANDO068 4.0
END DESCRIPTION:
XS GIS Cut Line= 3
      2811405.68     10248053.12      2810982.41     10248569.00
      2810755.67     10249053.14
#Sta/Elev= 30
  4332.7 1052.82  4539.4 1045.10  4595.3 1044.55  4624.0 1042.78  4694.9 1042.29
  4745.3 1043.70  4751.8 1043.44  4766.1 1040.07  4780.5 1038.23  4858.7 1032.18
  4879.5 1031.58  4908.2 1028.18  4972.1 1031.55  4986.4 1029.32  5005.0 1028.08
  5005.3 1027.58  5009.1 1028.08  5024.4 1029.71  5052.7 1030.52  5115.0 1034.73
  5126.7 1036.23  5292.1 1042.62  5429.1 1049.84  5446.2 1051.83  5451.9 1053.55
  5497.6 1058.88  5503.1 1058.09  5512.5 1059.90  5525.9 1060.22  5534.6 1061.58
#Mann=4,-1,0
  4332.7    0.05       0  5005.0    0.05       0  5009.1    0.05       0
  5497.6    0.12       0
Bank Sta=5005,5009.1
Exp/Cntr=0.3,0.1

Type RM Length L Ch R = 1,1500,500,500,500
BEGIN DESCRIPTION:
SANFERNANDO068 3.0
END DESCRIPTION:
XS GIS Cut Line= 3
      2810705.68     10248103.15      2810601.44     10248611.48
      2810705.69     10249003.14
#Sta/Elev= 30
  4481.1 1043.81  4542.3 1043.57  4556.7 1042.22  4624.0 1041.26  4652.4 1038.99
  4664.8 1039.40  4695.4 1036.91  4753.2 1034.54  4758.3 1035.52  4787.3 1035.64
  4803.6 1032.24  4854.0 1027.88  4859.1 1030.02  4899.3 1025.73  4904.5 1026.75
  4949.8 1023.40  4954.9 1024.12  4960.8 1022.97  5029.6 1022.21  5029.9 1021.71
  5033.8 1022.21  5043.1 1024.33  5069.8 1026.47  5192.3 1034.24  5208.7 1037.83
  5227.2 1040.28  5250.0 1039.99  5281.1 1044.40  5387.8 1052.13  5405.3 1054.43
#Mann=4,-1,0
  4481.1    0.05       0  5029.6    0.05       0  5033.8    0.05       0
  5069.8    0.12       0
Bank Sta=5029.6,5033.8
Exp/Cntr=0.3,0.1

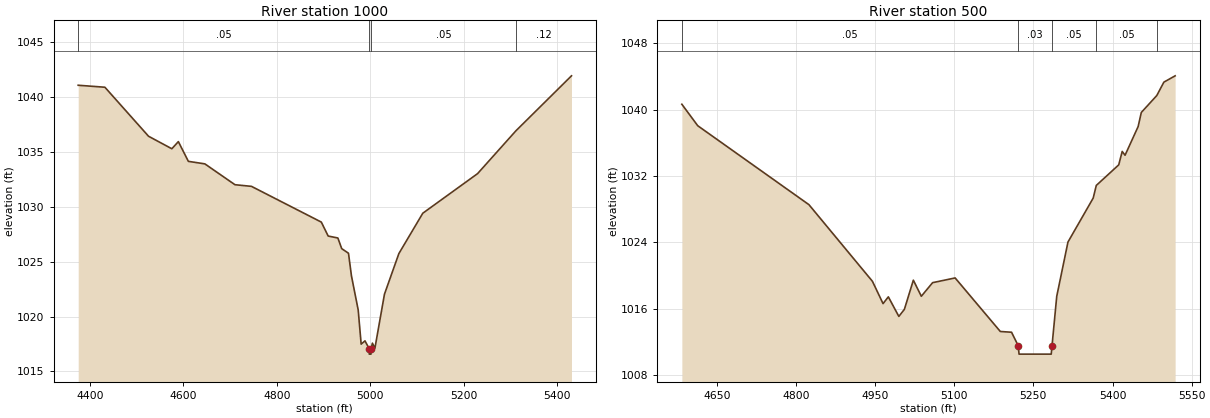
Type RM Length L Ch R = 1,1000,500,500,500
BEGIN DESCRIPTION:
SANFERNANDO068 2.0
END DESCRIPTION:
XS GIS Cut Line= 3
      2810655.68     10248253.11      2810159.74     10248633.79
      2810255.69     10249053.15
#Sta/Elev= 30
  4374.8 1041.10  4431.9 1040.92  4525.3 1036.45  4575.1 1035.31  4589.1 1035.96
  4610.5 1034.16  4645.8 1033.93  4710.2 1032.03  4745.5 1031.88  4895.0 1028.62
  4909.6 1027.35  4930.4 1027.17  4938.6 1026.20  4953.1 1025.78  4959.4 1023.73
  4973.9 1020.60  4980.2 1017.49  4988.4 1017.79  4997.3 1017.08  4997.6 1016.58
  5001.2 1016.58  5001.5 1017.08  5004.3 1017.58  5009.6 1017.11  5030.1 1022.05
  5060.9 1025.75  5112.1 1029.43  5229.3 1033.04  5311.2 1036.94  5430.2 1041.96
#Mann=4,-1,0
  4374.8    0.05       0  4997.3    0.03       0  5001.5    0.05       0
  5311.2    0.12       0
Bank Sta=4997.3,5001.5
Exp/Cntr=0.3,0.1

Type RM Length L Ch R = 1,500,0,0,0
BEGIN DESCRIPTION:
SANFERNANDO068 1.0
END DESCRIPTION:
XS GIS Cut Line= 3
      2810605.72     10248153.11      2810190.95     10248186.41
      2809705.72     10248003.12
#Sta/Elev= 30
  4583.9 1040.67  4614.0 1038.08  4824.7 1028.56  4945.1 1019.31  4965.2 1016.62
  4975.2 1017.44  4995.1 1015.08  5005.6 1015.93  5022.6 1019.45  5037.7 1017.51
  5059.1 1019.15  5101.8 1019.72  5187.4 1013.26  5208.7 1013.17  5221.4 1011.53
  5222.9 1010.53  5283.9 1010.53  5285.4 1011.53  5294.3 1017.49  5315.6 1024.05
  5363.4 1029.35  5369.3 1030.88  5411.8 1033.36  5418.4 1034.98  5423.8 1034.52
  5448.6 1037.98  5454.6 1039.68  5483.9 1041.72  5497.4 1043.34  5518.7 1044.10
#Mann=5,-1,0
  4583.9    0.05       0  5221.4    0.03       0  5285.4    0.05       0
  5369.3    0.05       0  5483.9    0.12       0
Bank Sta=5221.4,5285.4
Exp/Cntr=0.3,0.1

Chan Stop Cuts=-1