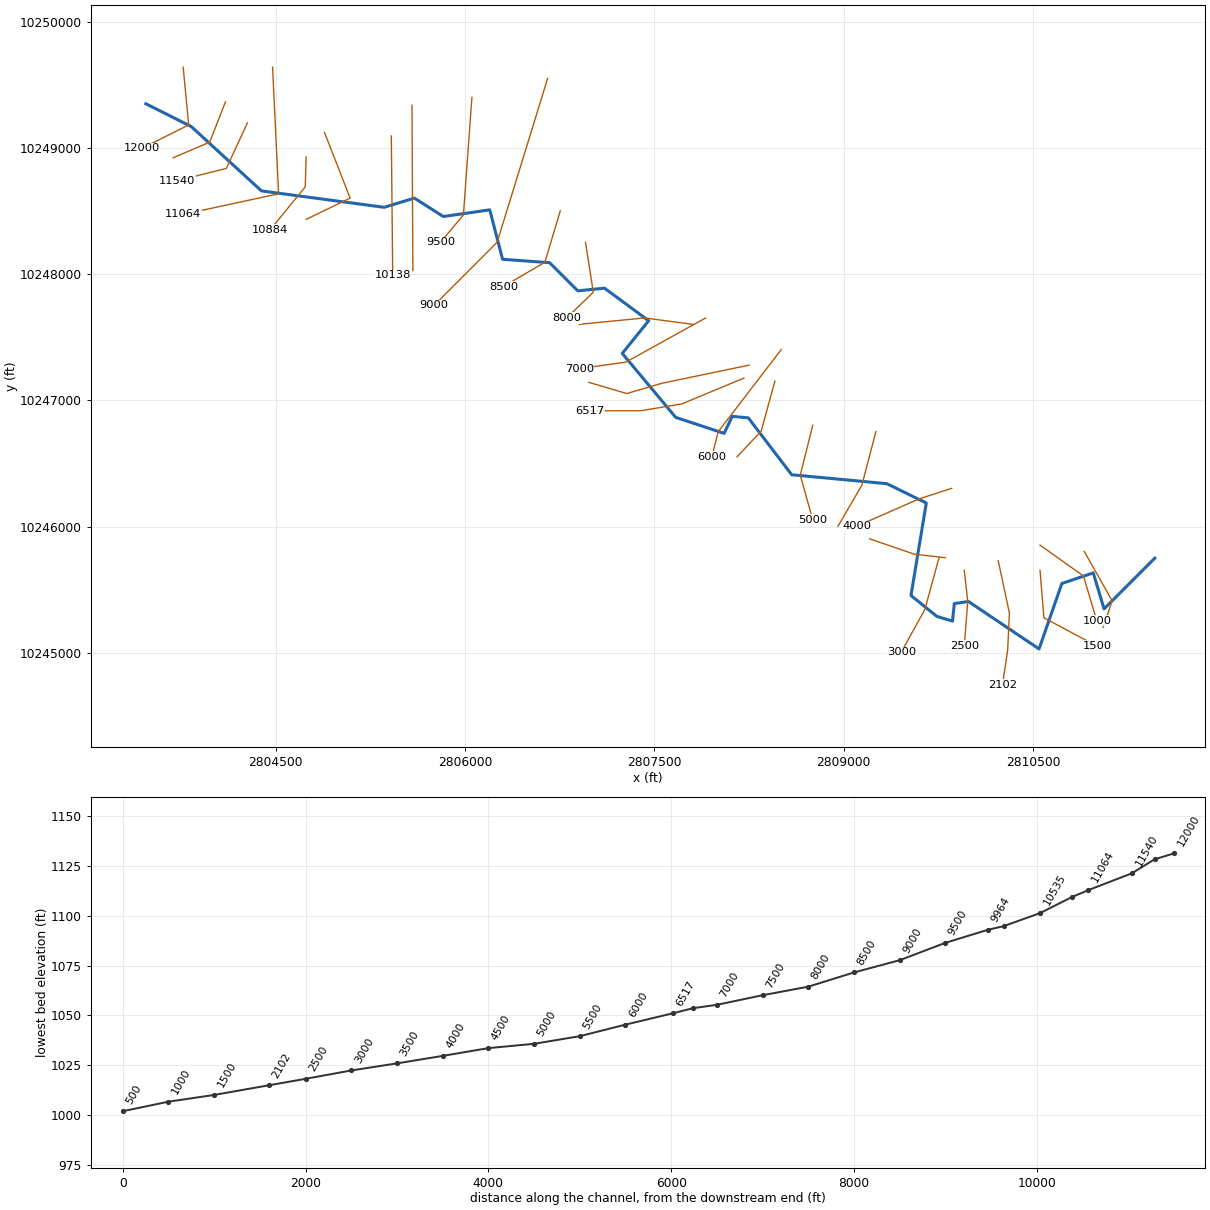
--- SANFERNANDO069.prj (project) ---

Proj Title=SANFERNANDO069 Base Level Engineering
Current Plan=p01
Default Exp/Contr=0.3,0.1
English Units
Geom File=g01
Flow File=f01
Plan File=p01
BEGIN DESCRIPTION:
SANFERNANDO069
END DESCRIPTION:

--- SANFERNANDO069.p01 (plan) ---

Plan Title=Multiple Run
Short Identifier=Multiple
Geom File=g01
Flow File=f01
Subcritical Flow
K Sum by GR= 0
Std Step Tol= 0.01
Critical Tol= 0.01
Num of Std Step Trials= 20
Max Error Tol= 0.3
Flow Tol Ratio= 0.001
Split Flow NTrial= 30
Split Flow Tol= 0.02
Split Flow Ratio= 0.02
Log Output Level= 0
Friction Slope Method= 1
Unsteady Friction Slope Method= 2
Unsteady Bridges Friction Slope Method= 1
Parabolic Critical Depth
Global Vel Dist=  1 , 1 , 1
Global Log Level= 0
CheckData=True
Encroach Param= -1, 0, 0, 0
BEGIN DESCRIPTION:
Multiple Run
END DESCRIPTION:

--- SANFERNANDO069.f01 (steady flow) ---

Flow Title=Multiple
Number of Profiles=7
Profile Names=10-year,25-year,50-year,1pct_min,100-year,1pct_plu,500-year
River Rch & RM= SANFERNANDO069,Reach-1,12000
     526     872    1034     679    1378    2796    1892
Boundary for River Rch & Prof#=SANFERNANDO069,Reach-1,1
Up Type=0
Dn Type=3
Dn Slope=0.005
Boundary for River Rch & Prof#=SANFERNANDO069,Reach-1,2
Up Type=0
Dn Type=3
Dn Slope=0.005
Boundary for River Rch & Prof#=SANFERNANDO069,Reach-1,3
Up Type=0
Dn Type=3
Dn Slope=0.005
Boundary for River Rch & Prof#=SANFERNANDO069,Reach-1,4
Up Type=0
Dn Type=3
Dn Slope=0.005
Boundary for River Rch & Prof#=SANFERNANDO069,Reach-1,5
Up Type=0
Dn Type=3
Dn Slope=0.005
Boundary for River Rch & Prof#=SANFERNANDO069,Reach-1,6
Up Type=0
Dn Type=3
Dn Slope=0.005
Boundary for River Rch & Prof#=SANFERNANDO069,Reach-1,7
Up Type=0
Dn Type=3
Dn Slope=0.005

--- SANFERNANDO069.g01 (geometry) ---

Geom Title=Existing Conditions

River Reach=SANFERNANDO069,Reach-1
Reach XY= 30
      2803472.75     10249352.00      2803833.00     10249171.00
      2804388.75     10248661.00      2805360.50     10248531.00
      2805600.00     10248604.00      2805829.25     10248458.00
      2806197.00     10248511.00      2806298.75     10248119.00
      2806671.50     10248092.00      2806894.00     10247869.00
      2807105.75     10247890.00      2807455.75     10247632.00
      2807246.75     10247373.00      2807669.50     10246866.00
      2808053.25     10246739.00      2808118.00     10246874.00
      2808245.00     10246862.00      2808588.75     10246411.00
      2809343.00     10246340.00      2809654.75     10246187.00
      2809533.50     10245454.00      2809738.75     10245288.00
      2809862.50     10245251.00      2809876.75     10245390.00
      2809989.25     10245406.00      2810548.00     10245030.00
      2810728.50     10245549.00      2810977.25     10245633.00
      2811062.75     10245348.00      2811464.50     10245750.00

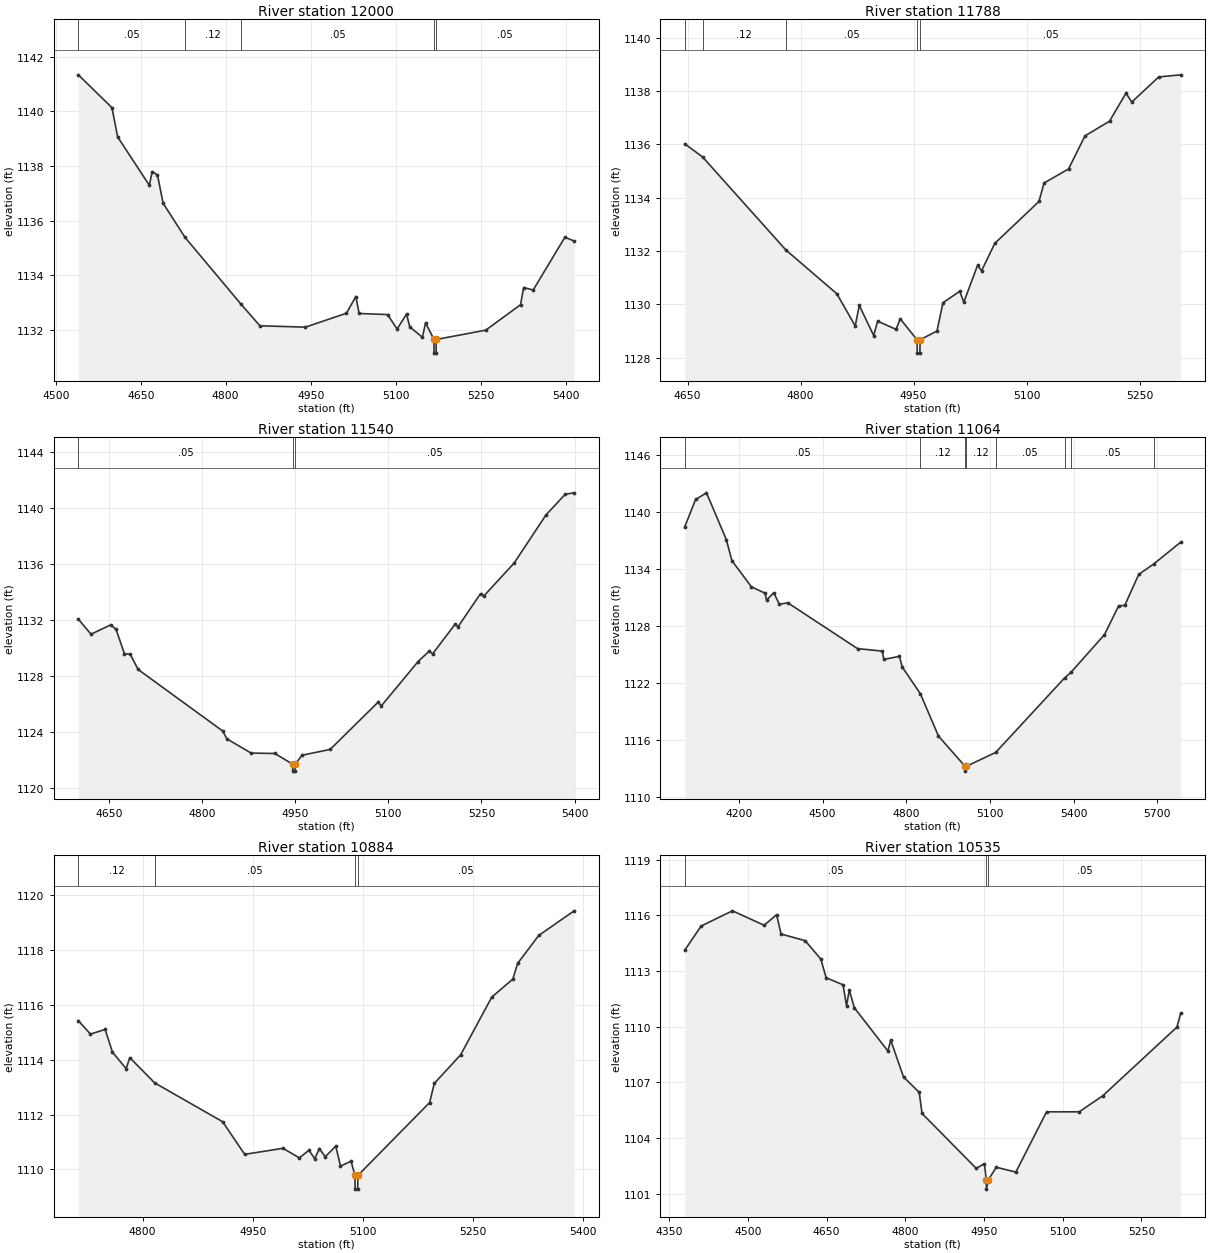
Type RM Length L Ch R = 1,12000,212,212,212
BEGIN DESCRIPTION:
SANFERNANDO069 24.0
END DESCRIPTION:
XS GIS Cut Line= 3
      2803768.75     10249642.18      2803812.31     10249184.15
      2803441.07     10248998.20
#Sta/Elev= 30
  4539.9 1141.33  4599.2 1140.13  4609.3 1139.06  4665.2 1137.29  4670.3 1137.79
  4679.6 1137.67  4689.6 1136.63  4728.4 1135.38  4826.7 1132.95  4860.4 1132.15
  4940.8 1132.10  5013.2 1132.61  5029.8 1133.22  5035.6 1132.60  5085.9 1132.56
  5102.6 1132.03  5119.3 1132.58  5125.0 1132.11  5147.3 1131.73  5152.9 1132.26
  5167.7 1131.65  5167.9 1131.15  5171.4 1131.15  5171.7 1131.65  5259.1 1131.99
  5320.5 1132.92  5326.1 1133.55  5342.9 1133.46  5398.9 1135.39  5415.2 1135.25
#Mann=5,-1,0
  4539.9    0.05       0  4728.4    0.12       0  4826.7    0.05       0
  5167.7    0.03       0  5171.7    0.05       0
Bank Sta=5167.7,5171.7
Exp/Cntr=0.3,0.1

Type RM Length L Ch R = 1,11788,248,248,248
BEGIN DESCRIPTION:
Mapping XS a5f66270
END DESCRIPTION:
XS GIS Cut Line= 3
      2804103.81     10249367.17      2803978.81     10249047.72
      2803688.94     10248923.49
#Sta/Elev= 30
  4646.2 1136.02  4669.8 1135.53  4780.4 1132.04  4848.0 1130.40  4872.5 1129.19
  4877.9 1129.96  4897.0 1128.83  4902.3 1129.37  4926.8 1129.06  4932.2 1129.46
  4954.6 1128.67  4954.9 1128.17  4958.4 1128.17  4958.6 1128.67  4981.1 1129.00
  4989.0 1130.06  5011.3 1130.49  5016.7 1130.08  5034.9 1131.46  5040.3 1131.26
  5057.9 1132.29  5116.5 1133.86  5123.2 1134.55  5155.8 1135.08  5177.6 1136.32
  5210.2 1136.87  5232.0 1137.92  5239.8 1137.59  5275.5 1138.53  5304.6 1138.61
#Mann=5,-1,0
  4646.2    0.05       0  4669.8    0.12       0  4780.4    0.05       0
  4954.6    0.05       0  4958.6    0.05       0
Bank Sta=4954.6,4958.6
Exp/Cntr=0.3,0.1

Type RM Length L Ch R = 1,11540,476,476,476
BEGIN DESCRIPTION:
Mapping XS e2d4322b
END DESCRIPTION:
XS GIS Cut Line= 3
      2804277.43     10249200.51      2804110.76     10248839.39
      2803721.86     10248742.17
#Sta/Elev= 30
  4600.7 1132.04  4621.1 1130.96  4652.9 1131.63  4661.5 1131.30  4674.9 1129.57
  4684.4 1129.52  4697.0 1128.44  4833.1 1124.05  4840.1 1123.48  4879.0 1122.47
  4917.2 1122.44  4945.8 1121.68  4946.1 1121.18  4949.6 1121.18  4949.8 1121.68
  4961.3 1122.32  5006.3 1122.73  5083.6 1126.11  5088.7 1125.84  5148.0 1129.01
  5166.0 1129.76  5171.2 1129.55  5207.3 1131.66  5212.4 1131.50  5248.5 1133.86
  5253.6 1133.68  5302.6 1136.04  5354.1 1139.49  5385.0 1140.96  5399.3 1141.06
#Mann=3,-1,0
  4600.7    0.05       0  4945.8    0.05       0  4949.8    0.05       0
Bank Sta=4945.8,4949.8
Exp/Cntr=0.3,0.1

Type RM Length L Ch R = 1,11064,180,180,180
BEGIN DESCRIPTION:
Mapping XS 2d5dad35
END DESCRIPTION:
XS GIS Cut Line= 3
      2804476.79     10249641.81      2804524.58     10248638.35
      2803768.75     10248474.92
#Sta/Elev= 30
  4006.0 1138.47  4044.7 1141.33  4083.8 1142.03  4154.9 1137.11  4174.9 1134.90
  4245.0 1132.14  4294.0 1131.48  4299.0 1130.75  4325.1 1131.52  4345.1 1130.31
  4375.1 1130.47  4625.4 1125.65  4714.5 1125.39  4719.5 1124.51  4775.6 1124.84
  4785.6 1123.72  4850.6 1120.91  4915.7 1116.45  5011.2 1113.27  5011.4 1112.77
  5015.2 1113.27  5120.9 1114.74  5367.6 1122.56  5391.4 1123.18  5510.8 1127.12
  5562.0 1130.16  5583.5 1130.19  5633.6 1133.45  5687.1 1134.54  5783.9 1136.84
#Mann=8,-1,0
  4006.0    0.05       0  4850.6    0.12       0  5011.2    0.07       0
  5015.2    0.12       0  5120.9    0.05       0  5367.6    0.12       0
  5391.4    0.05       0  5687.1    0.12       0
Bank Sta=5011.2,5015.2
Exp/Cntr=0.3,0.1

Type RM Length L Ch R = 1,10884,349,349,349
BEGIN DESCRIPTION:
Mapping XS befa999f
END DESCRIPTION:
XS GIS Cut Line= 3
      2804742.70     10248929.63      2804735.76     10248693.56
      2804458.01     10248353.31
#Sta/Elev= 30
  4712.5 1115.43  4729.0 1114.94  4749.0 1115.11  4759.0 1114.28  4777.6 1113.68
  4782.6 1114.08  4816.4 1113.16  4909.1 1111.74  4939.1 1110.55  4991.4 1110.77
  5013.6 1110.42  5026.7 1110.70  5034.5 1110.39  5040.9 1110.76  5048.8 1110.46
  5063.2 1110.85  5069.6 1110.12  5084.0 1110.30  5089.3 1109.78  5089.5 1109.28
  5093.0 1109.28  5093.3 1109.78  5191.0 1112.44  5197.4 1113.14  5233.2 1114.18
  5275.7 1116.29  5304.4 1116.95  5310.9 1117.52  5339.6 1118.54  5387.9 1119.44
#Mann=4,-1,0
  4712.5    0.12       0  4816.4    0.05       0  5089.3    0.05       0
  5093.3    0.05       0
Bank Sta=5089.3,5093.3
Exp/Cntr=0.3,0.1

Type RM Length L Ch R = 1,10535,397,397,397
BEGIN DESCRIPTION:
Mapping XS 180d4226
END DESCRIPTION:
XS GIS Cut Line= 3
      2804888.17     10249123.95      2805091.14     10248604.22
      2804743.21     10248435.60
#Sta/Elev= 30
  4380.0 1114.13  4411.1 1115.43  4470.8 1116.25  4531.2 1115.47  4554.9 1116.04
  4563.4 1115.00  4609.3 1114.64  4639.1 1113.65  4649.3 1112.64  4681.5 1112.26
  4688.1 1111.13  4693.4 1111.98  4703.0 1111.02  4766.9 1108.69  4772.3 1109.27
  4796.7 1107.29  4826.6 1106.46  4832.0 1105.32  4935.2 1102.36  4950.8 1102.61
  4954.3 1101.74  4954.6 1101.24  4958.3 1101.74  4973.3 1102.42  5010.7 1102.16
  5069.2 1105.41  5131.4 1105.41  5176.5 1106.28  5317.6 1109.98  5324.6 1110.72
#Mann=3,-1,0
  4380.0    0.05       0  4954.3    0.05       0  4958.3    0.05       0
Bank Sta=4954.3,4958.3
Exp/Cntr=0.3,0.1

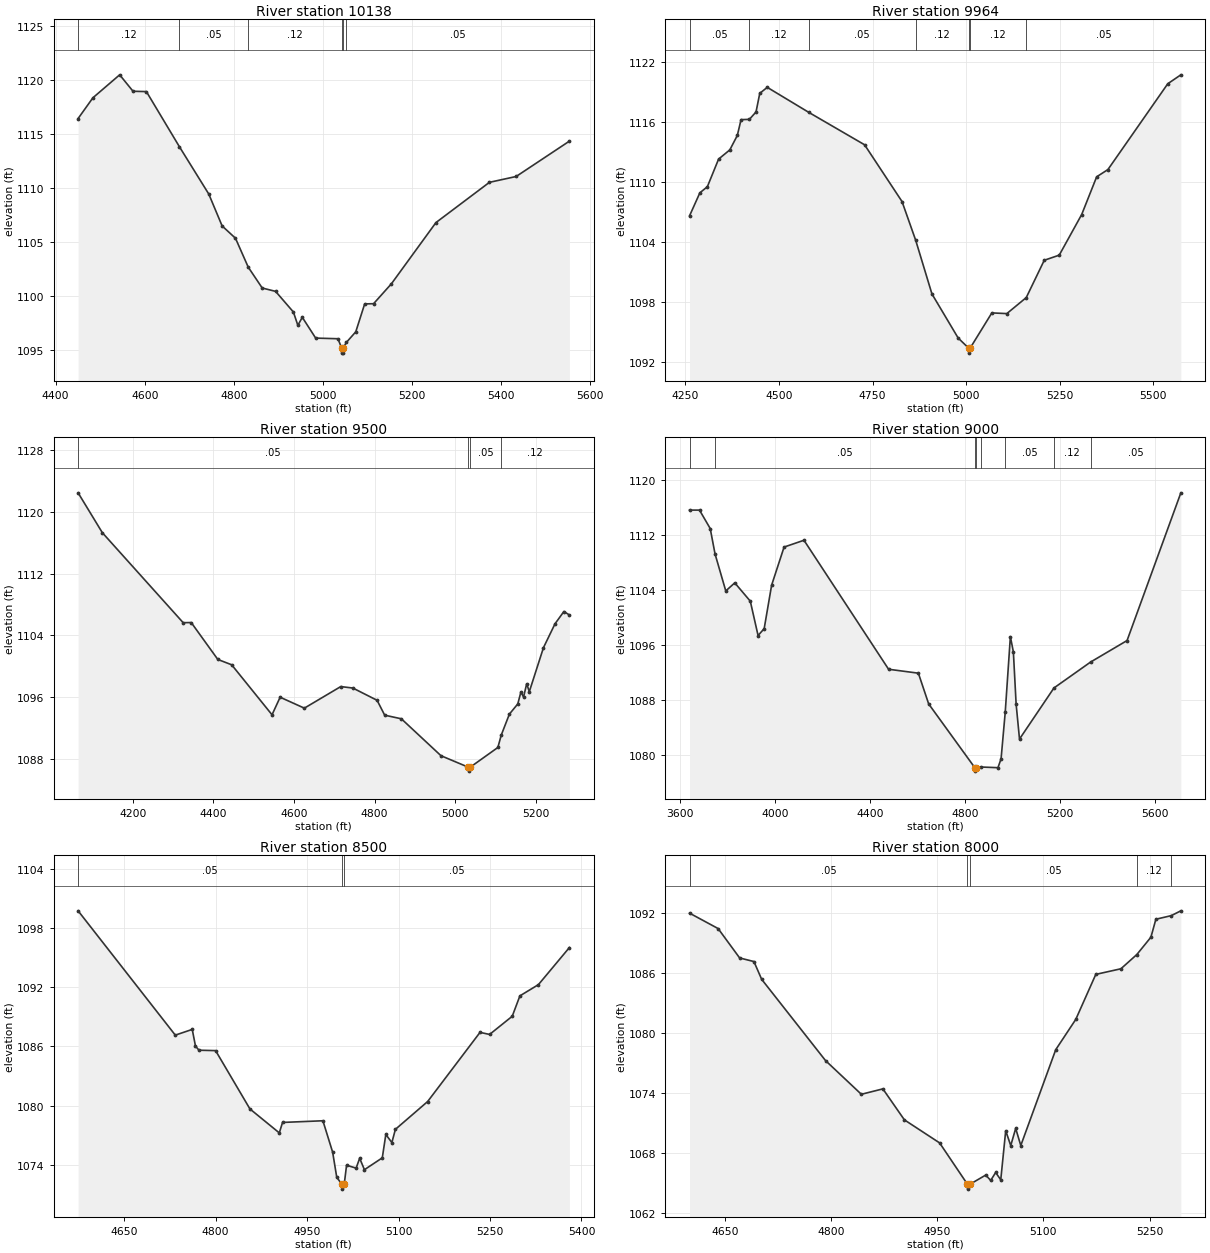
Type RM Length L Ch R = 1,10138,174,174,174
BEGIN DESCRIPTION:
Mapping XS 2f26f4ab
END DESCRIPTION:
XS GIS Cut Line= 2
      2805417.35     10249096.39      2805428.38     10247993.55
#Sta/Elev= 30
  4450.5 1116.41  4483.8 1118.33  4543.8 1120.45  4573.8 1118.93  4603.8 1118.90
  4677.8 1113.81  4743.8 1109.43  4773.8 1106.48  4803.8 1105.34  4832.4 1102.67
  4863.8 1100.74  4893.8 1100.43  4933.8 1098.52  4943.8 1097.29  4953.8 1098.03
  4983.8 1096.11  5033.8 1096.05  5041.8 1095.22  5042.1 1094.72  5045.6 1094.72
  5045.8 1095.22  5052.9 1095.72  5073.8 1096.69  5093.8 1099.27  5113.8 1099.29
  5153.8 1101.13  5253.8 1106.79  5373.8 1110.51  5433.8 1111.05  5553.4 1114.32
#Mann=6,-1,0
  4450.5    0.12       0  4677.8    0.05       0  4832.4    0.12       0
  5041.8    0.07       0  5045.8    0.12       0  5052.9    0.05       0
Bank Sta=5041.8,5045.8
Exp/Cntr=0.3,0.1

Type RM Length L Ch R = 1,9964,464,464,464
BEGIN DESCRIPTION:
Mapping XS 37a0dce3
END DESCRIPTION:
XS GIS Cut Line= 2
      2805581.16     10249340.70      2805588.10     10248028.22
#Sta/Elev= 30
  4260.9 1106.61  4288.5 1108.91  4308.5 1109.52  4338.5 1112.28  4368.5 1113.20
  4388.5 1114.64  4398.5 1116.22  4420.7 1116.25  4438.5 1116.99  4448.5 1118.85
  4468.5 1119.45  4579.4 1116.95  4728.5 1113.71  4828.5 1108.04  4865.1 1104.16
  4908.5 1098.80  4978.5 1094.40  5006.5 1093.39  5006.8 1092.89  5010.5 1093.39
  5068.5 1096.91  5108.5 1096.84  5160.4 1098.44  5208.5 1102.17  5248.5 1102.68
  5308.5 1106.74  5348.5 1110.51  5378.5 1111.23  5538.5 1119.81  5573.4 1120.70
#Mann=7,-1,0
  4260.9    0.05       0  4420.7    0.12       0  4579.4    0.05       0
  4865.1    0.12       0  5006.5    0.07       0  5010.5    0.12       0
  5160.4    0.05       0
Bank Sta=5006.5,5010.5
Exp/Cntr=0.3,0.1

Type RM Length L Ch R = 1,9500,500,500,500
BEGIN DESCRIPTION:
SANFERNANDO069 19.0
END DESCRIPTION:
XS GIS Cut Line= 3
      2806055.68     10249403.10      2805988.37     10248469.92
      2805805.69     10248253.12
#Sta/Elev= 30
  4064.4 1122.48  4124.5 1117.31  4325.1 1105.63  4345.1 1105.65  4411.1 1100.86
  4445.4 1100.17  4545.6 1093.68  4565.7 1095.96  4625.8 1094.54  4716.1 1097.34
  4746.2 1097.15  4806.3 1095.56  4825.1 1093.63  4866.5 1093.16  4964.8 1088.37
  5033.1 1086.87  5033.3 1086.37  5037.1 1086.87  5106.0 1089.44  5114.4 1091.05
  5134.6 1093.77  5155.4 1095.09  5163.2 1096.64  5169.7 1095.98  5177.5 1097.71
  5184.0 1096.68  5219.2 1102.40  5247.8 1105.49  5269.8 1107.08  5283.5 1106.63
#Mann=4,-1,0
  4064.4    0.05       0  5033.1    0.03       0  5037.1    0.05       0
  5114.4    0.12       0
Bank Sta=5033.1,5037.1
Exp/Cntr=0.3,0.1

Type RM Length L Ch R = 1,9000,500,500,500
BEGIN DESCRIPTION:
SANFERNANDO069 18.0
END DESCRIPTION:
XS GIS Cut Line= 3
      2806655.70     10249553.16      2806255.78     10248254.54
      2805755.67     10247753.10
#Sta/Elev= 30
  3641.2 1115.59  3683.1 1115.59  3728.2 1112.91  3748.5 1109.22  3793.6 1103.85
  3831.5 1105.02  3896.8 1102.36  3929.5 1097.37  3955.2 1098.37  3986.5 1104.68
  4038.9 1110.22  4122.6 1111.21  4478.6 1092.47  4603.9 1091.90  4647.3 1087.43
  4841.4 1078.17  4841.6 1077.67  4845.4 1078.17  4865.4 1078.27  4938.7 1078.17
  4951.9 1079.46  4969.3 1086.21  4991.0 1097.21  5003.6 1094.99  5015.2 1087.40
  5029.4 1082.33  5174.3 1089.75  5328.2 1093.51  5481.9 1096.64  5708.2 1118.10
#Mann=8,-1,0
  3641.2    0.12       0  3748.5    0.05       0  4841.4    0.03       0
  4845.4    0.05       0  4865.4    0.12       0  4969.3    0.05       0
  5174.3    0.12       0  5328.2    0.05       0
Bank Sta=4841.4,4845.4
Exp/Cntr=0.3,0.1

Type RM Length L Ch R = 1,8500,500,500,500
BEGIN DESCRIPTION:
SANFERNANDO069 17.0
END DESCRIPTION:
XS GIS Cut Line= 3
      2806755.68     10248503.11      2806633.64     10248095.39
      2806305.65     10247903.09
#Sta/Elev= 30
  4574.4 1099.75  4733.8 1087.15  4761.6 1087.73  4766.9 1086.04  4772.7 1085.62
  4799.9 1085.58  4856.2 1079.67  4904.4 1077.24  4909.7 1078.30  4975.9 1078.47
  4991.9 1075.28  4998.6 1072.74  5006.9 1072.04  5007.2 1071.54  5010.9 1072.04
  5014.7 1073.96  5030.4 1073.67  5036.2 1074.67  5044.0 1073.51  5073.3 1074.71
  5079.1 1077.08  5089.0 1076.26  5094.8 1077.60  5147.7 1080.42  5233.6 1087.43
  5249.3 1087.22  5286.4 1089.06  5299.0 1091.13  5329.4 1092.27  5380.2 1096.03
#Mann=3,-1,0
  4574.4    0.05       0  5006.9    0.05       0  5010.9    0.05       0
Bank Sta=5006.9,5010.9
Exp/Cntr=0.3,0.1

Type RM Length L Ch R = 1,8000,500,500,500
BEGIN DESCRIPTION:
SANFERNANDO069 16.0
END DESCRIPTION:
XS GIS Cut Line= 3
      2806955.69     10248253.07      2807017.17     10247857.82
      2806805.71     10247653.14
#Sta/Elev= 30
  4600.0 1091.94  4640.4 1090.40  4670.8 1087.47  4691.0 1087.11  4701.9 1085.34
  4792.2 1077.23  4842.8 1073.87  4873.2 1074.41  4903.6 1071.32  4953.4 1069.02
  4992.6 1064.91  4992.9 1064.41  4996.6 1064.91  5018.5 1065.81  5025.6 1065.28
  5032.6 1066.07  5039.8 1065.34  5046.8 1070.24  5053.9 1068.75  5060.9 1070.47
  5068.1 1068.76  5117.5 1078.32  5145.8 1081.34  5174.1 1085.83  5209.6 1086.39
  5232.1 1087.81  5252.0 1089.54  5259.0 1091.33  5280.7 1091.69  5294.3 1092.17
#Mann=5,-1,0
  4600.0    0.05       0  4992.6    0.05       0  4996.6    0.05       0
  5232.1    0.12       0  5280.7    0.05       0
Bank Sta=4992.6,4996.6
Exp/Cntr=0.3,0.1

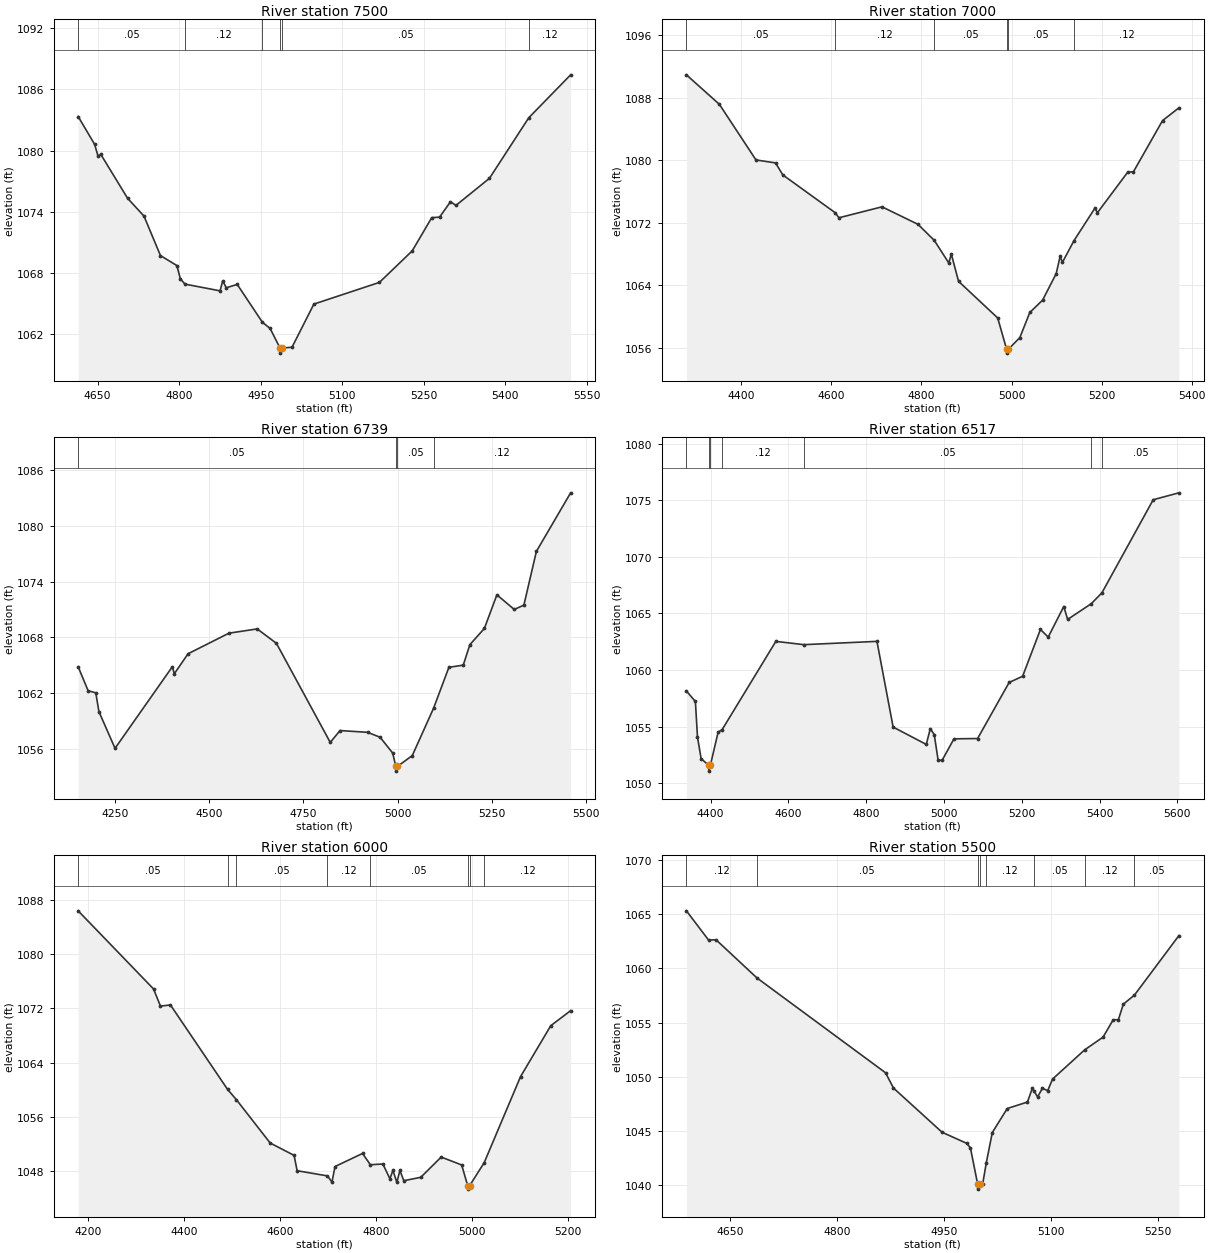
Type RM Length L Ch R = 1,7500,500,500,500
BEGIN DESCRIPTION:
SANFERNANDO069 15.0
END DESCRIPTION:
XS GIS Cut Line= 3
      2807805.71     10247603.11      2807423.20     10247654.14
      2806905.71     10247603.11
#Sta/Elev= 30
  4614.1 1083.34  4644.4 1080.61  4650.7 1079.44  4655.7 1079.63  4704.9 1075.33
  4735.2 1073.57  4765.5 1069.70  4795.7 1068.72  4802.0 1067.43  4810.5 1066.90
  4875.1 1066.24  4880.1 1067.23  4886.5 1066.54  4906.7 1066.87  4953.0 1063.16
  4967.2 1062.55  4985.4 1060.63  4985.7 1060.13  4989.4 1060.63  5007.5 1060.71
  5047.7 1064.94  5168.3 1067.07  5228.6 1070.16  5264.5 1073.42  5278.9 1073.47
  5299.0 1074.98  5309.0 1074.62  5370.7 1077.28  5443.0 1083.22  5520.0 1087.43
#Mann=6,-1,0
  4614.1    0.05       0  4810.5    0.12       0  4953.0    0.05       0
  4985.4    0.05       0  4989.4    0.05       0  5443.0    0.12       0
Bank Sta=4985.4,4989.4
Exp/Cntr=0.3,0.1

Type RM Length L Ch R = 1,7000,261,261,261
BEGIN DESCRIPTION:
SANFERNANDO069 14.0
END DESCRIPTION:
XS GIS Cut Line= 3
      2807905.65     10247653.09      2807274.01     10247303.15
      2806905.69     10247253.11
#Sta/Elev= 30
  4277.9 1090.94  4351.1 1087.17  4432.4 1080.05  4475.9 1079.67  4491.9 1078.14
  4608.0 1073.31  4616.7 1072.65  4712.3 1074.05  4792.3 1071.81  4828.5 1069.75
  4860.6 1066.87  4866.3 1068.00  4882.3 1064.52  4969.3 1059.83  4989.1 1055.83
  4989.3 1055.33  4993.1 1055.83  5018.5 1057.32  5040.6 1060.53  5069.0 1062.11
  5099.2 1065.50  5108.0 1067.73  5113.0 1066.94  5138.8 1069.73  5185.5 1073.90
  5190.6 1073.28  5258.0 1078.48  5270.8 1078.54  5335.5 1085.09  5371.7 1086.71
#Mann=6,-1,0
  4277.9    0.05       0  4608.0    0.12       0  4828.5    0.05       0
  4989.1    0.05       0  4993.1    0.05       0  5138.8    0.12       0
Bank Sta=4989.1,4993.1
Exp/Cntr=0.3,0.1

Type RM Length L Ch R = 1,6739,222,222,222
BEGIN DESCRIPTION:
Mapping XS 892bac17
END DESCRIPTION:
XS GIS Cut Line= 4
      2808251.62     10247279.96      2807562.17     10247136.61
      2807282.30     10247054.70      2806981.94     10247143.44
#Sta/Elev= 30
  4151.1 1064.85  4177.6 1062.28  4198.0 1062.05  4206.2 1060.04  4249.1 1056.09
  4401.5 1064.86  4406.6 1064.10  4443.2 1066.25  4551.8 1068.46  4627.0 1068.92
  4678.1 1067.37  4821.1 1056.73  4847.3 1058.00  4920.3 1057.81  4953.7 1057.28
  4987.1 1055.58  4995.5 1054.14  4995.8 1053.64  4999.5 1054.14  5039.2 1055.31
  5095.7 1060.39  5136.5 1064.79  5174.7 1065.03  5192.3 1067.23  5230.8 1068.97
  5264.1 1072.58  5310.2 1071.01  5335.8 1071.47  5369.1 1077.25  5460.1 1083.54
#Mann=4,-1,0
  4151.1    0.05       0  4995.5    0.05       0  4999.5    0.05       0
  5095.7    0.12       0
Bank Sta=4995.5,4999.5
Exp/Cntr=0.3,0.1

Type RM Length L Ch R = 1,6517,517,517,517
BEGIN DESCRIPTION:
Mapping XS 51aa8f19
END DESCRIPTION:
XS GIS Cut Line= 4
      2808210.61     10247177.55      2807719.17     10246972.79
      2807391.52     10246918.18      2806989.69     10246918.18
#Sta/Elev= 30
  4337.7 1058.15  4360.8 1057.22  4366.2 1054.08  4375.5 1052.18  4395.2 1051.57
  4395.5 1051.07  4399.2 1051.57  4419.3 1054.52  4429.5 1054.73  4567.7 1062.53
  4639.7 1062.24  4827.7 1062.53  4869.3 1054.96  4954.5 1053.43  4964.9 1054.82
  4975.0 1054.30  4985.1 1052.02  4995.3 1052.03  5025.7 1053.92  5086.5 1053.95
  5167.6 1058.90  5202.3 1059.45  5248.1 1063.58  5268.1 1062.91  5308.1 1065.61
  5318.1 1064.47  5378.9 1065.86  5406.2 1066.82  5538.1 1075.04  5604.1 1075.65
#Mann=7,-1,0
  4337.7    0.05       0  4395.2    0.03       0  4399.2    0.05       0
  4429.5    0.12       0  4639.7    0.05       0  5378.9    0.12       0
  5406.2    0.05       0
Bank Sta=4395.2,4399.2
Exp/Cntr=0.3,0.1

Type RM Length L Ch R = 1,6000,500,500,500
BEGIN DESCRIPTION:
SANFERNANDO069 12.0
END DESCRIPTION:
XS GIS Cut Line= 3
      2808505.71     10247403.14      2808006.99     10246752.36
      2807955.70     10246553.16
#Sta/Elev= 30
  4180.1 1086.38  4337.0 1074.88  4351.5 1072.35  4372.3 1072.52  4491.2 1060.09
  4509.4 1058.59  4580.0 1052.19  4629.8 1050.37  4636.1 1048.11  4699.2 1047.35
  4708.7 1046.44  4715.0 1048.73  4772.3 1050.65  4788.7 1048.99  4814.7 1049.10
  4829.3 1046.93  4835.6 1048.16  4843.8 1046.39  4850.1 1048.15  4858.3 1046.64
  4893.6 1047.14  4936.1 1050.12  4978.8 1048.96  4991.3 1045.90  4991.6 1045.40
  4995.3 1045.90  5025.7 1049.30  5101.4 1061.97  5164.4 1069.47  5205.7 1071.68
#Mann=8,-1,0
  4180.1    0.05       0  4491.2    0.12       0  4509.4    0.05       0
  4699.2    0.12       0  4788.7    0.05       0  4991.3    0.05       0
  4995.3    0.05       0  5025.7    0.12       0
Bank Sta=4991.3,4995.3
Exp/Cntr=0.3,0.1

Type RM Length L Ch R = 1,5500,500,500,500
BEGIN DESCRIPTION:
SANFERNANDO069 11.0
END DESCRIPTION:
XS GIS Cut Line= 3
      2808455.68     10247153.09      2808347.02     10246756.92
      2808155.65     10246553.08
#Sta/Elev= 30
  4589.2 1065.31  4620.3 1062.61  4630.7 1062.64  4688.0 1059.12  4868.4 1050.36
  4879.5 1048.95  4947.6 1044.87  4982.1 1043.85  4987.3 1043.44  4997.4 1040.12
  4997.6 1039.62  5001.4 1040.12  5004.6 1040.12  5009.6 1042.04  5018.0 1044.84
  5039.0 1047.06  5067.3 1047.66  5074.2 1048.94  5076.9 1048.64  5081.5 1048.13
  5088.3 1048.93  5095.7 1048.71  5102.5 1049.78  5147.6 1052.48  5173.3 1053.65
  5187.5 1055.25  5194.8 1055.26  5201.7 1056.69  5217.3 1057.53  5279.6 1063.02
#Mann=8,-1,0
  4589.2    0.12       0  4688.0    0.05       0  4997.4    0.03       0
  5001.4    0.05       0  5009.6    0.12       0  5076.9    0.05       0
  5147.6    0.12       0  5217.3    0.05       0
Bank Sta=4997.4,5001.4
Exp/Cntr=0.3,0.1

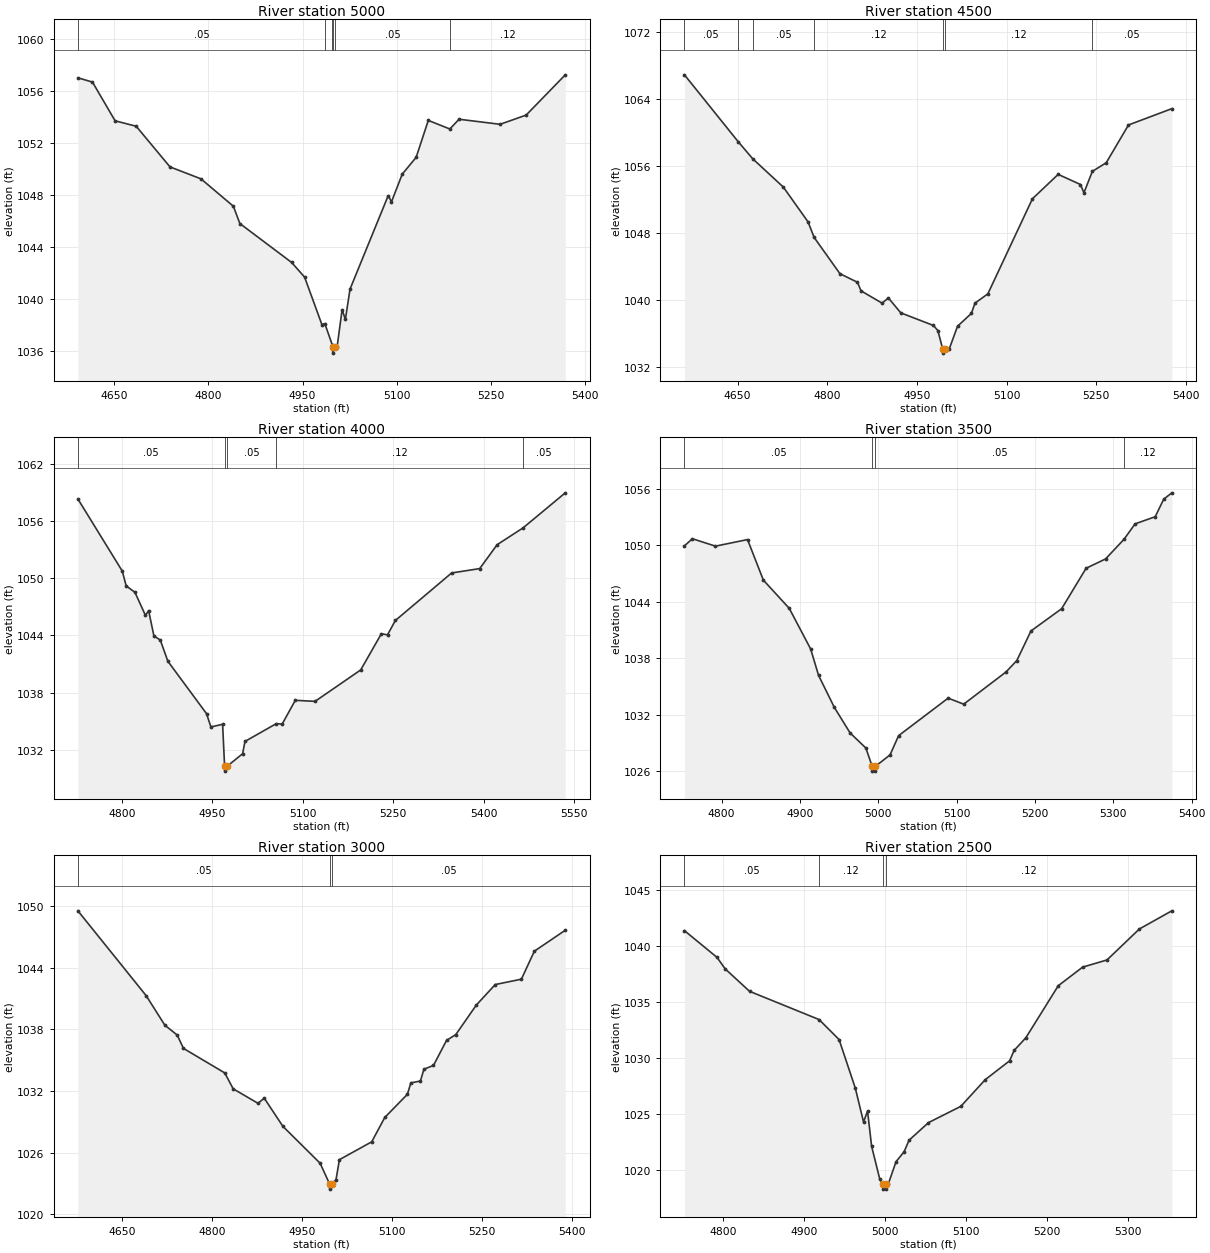
Type RM Length L Ch R = 1,5000,500,500,500
BEGIN DESCRIPTION:
SANFERNANDO069 10.0
END DESCRIPTION:
XS GIS Cut Line= 3
      2808755.69     10246803.13      2808656.43     10246407.69
      2808755.68     10246053.12
#Sta/Elev= 30
  4592.3 1057.00  4615.5 1056.67  4651.5 1053.69  4685.1 1053.27  4738.9 1050.14
  4788.2 1049.22  4839.8 1047.11  4850.1 1045.78  4932.6 1042.78  4953.2 1041.65
  4980.7 1038.00  4985.4 1038.07  4997.2 1036.44  4997.8 1036.30  4998.0 1035.80
  5001.8 1036.30  5005.0 1036.30  5012.9 1039.15  5018.1 1038.39  5025.5 1040.73
  5086.3 1047.93  5091.5 1047.45  5108.6 1049.58  5130.8 1050.88  5150.1 1053.72
  5184.4 1053.06  5199.1 1053.81  5264.4 1053.42  5305.9 1054.13  5368.2 1057.23
#Mann=6,-1,0
  4592.3    0.05       0  4985.4    0.12       0  4997.2    0.05       0
  4997.8    0.05       0  5001.8    0.05       0  5184.4    0.12       0
Bank Sta=4997.8,5001.8
Exp/Cntr=0.3,0.1

Type RM Length L Ch R = 1,4500,500,500,500
BEGIN DESCRIPTION:
SANFERNANDO069 9.0
END DESCRIPTION:
XS GIS Cut Line= 3
      2809255.67     10246753.07      2809144.48     10246328.59
      2808955.67     10246003.09
#Sta/Elev= 30
  4561.2 1066.88  4651.0 1058.90  4675.3 1056.86  4726.6 1053.47  4767.9 1049.32
  4778.0 1047.47  4821.2 1043.13  4850.6 1042.10  4856.5 1041.08  4891.7 1039.61
  4902.3 1040.23  4923.0 1038.45  4977.7 1036.94  4985.0 1036.33  4993.1 1034.14
  4993.3 1033.64  4997.1 1034.14  5004.1 1034.15  5017.9 1036.85  5041.0 1038.38
  5047.1 1039.61  5068.6 1040.72  5143.2 1052.08  5186.2 1054.99  5223.5 1053.78
  5229.3 1052.79  5243.4 1055.35  5266.6 1056.38  5303.8 1060.89  5376.3 1062.84
#Mann=7,-1,0
  4561.2    0.05       0  4651.0    0.12       0  4675.3    0.05       0
  4778.0    0.12       0  4993.1    0.07       0  4997.1    0.12       0
  5243.4    0.05       0
Bank Sta=4993.1,4997.1
Exp/Cntr=0.3,0.1

Type RM Length L Ch R = 1,4000,500,500,500
BEGIN DESCRIPTION:
SANFERNANDO069 8.0
END DESCRIPTION:
XS GIS Cut Line= 3
      2809855.71     10246303.12      2809595.67     10246219.02
      2809105.73     10246003.13
#Sta/Elev= 30
  4726.7 1058.34  4800.3 1050.77  4806.8 1049.21  4821.3 1048.54  4838.8 1046.11
  4844.0 1046.62  4852.8 1043.96  4863.4 1043.52  4876.0 1041.29  4940.1 1035.79
  4947.4 1034.39  4966.8 1034.67  4970.1 1030.25  4970.3 1029.75  4974.1 1030.25
  5000.0 1031.58  5003.9 1032.87  5055.9 1034.74  5065.6 1034.69  5087.4 1037.19
  5120.2 1037.08  5195.9 1040.38  5230.2 1044.18  5240.4 1044.07  5253.5 1045.58
  5346.8 1050.57  5393.4 1051.03  5422.3 1053.54  5465.4 1055.31  5535.4 1058.99
#Mann=5,-1,0
  4726.7    0.05       0  4970.1    0.05       0  4974.1    0.05       0
  5055.9    0.12       0  5465.4    0.05       0
Bank Sta=4970.1,4974.1
Exp/Cntr=0.3,0.1

Type RM Length L Ch R = 1,3500,500,500,500
BEGIN DESCRIPTION:
SANFERNANDO069 7.0
END DESCRIPTION:
XS GIS Cut Line= 3
      2809805.69     10245753.11      2809560.00     10245781.28
      2809205.66     10245903.12
#Sta/Elev= 30
  4752.7 1049.95  4762.8 1050.71  4792.3 1049.92  4833.2 1050.62  4853.4 1046.31
  4886.5 1043.30  4913.8 1038.98  4923.8 1036.19  4943.9 1032.79  4964.1 1030.06
  4984.2 1028.46  4992.3 1026.50  4992.5 1026.00  4996.0 1026.00  4996.3 1026.50
  5015.1 1027.73  5026.0 1029.77  5089.2 1033.76  5109.1 1033.12  5163.2 1036.55
  5176.9 1037.76  5194.9 1040.90  5234.1 1043.27  5265.3 1047.57  5290.1 1048.56
  5313.7 1050.65  5327.8 1052.29  5353.5 1053.05  5364.3 1054.91  5374.7 1055.59
#Mann=4,-1,0
  4752.7    0.05       0  4992.3    0.05       0  4996.3    0.05       0
  5313.7    0.12       0
Bank Sta=4992.3,4996.3
Exp/Cntr=0.3,0.1

Type RM Length L Ch R = 1,3000,500,500,500
BEGIN DESCRIPTION:
SANFERNANDO069 6.0
END DESCRIPTION:
XS GIS Cut Line= 3
      2809755.68     10245753.10      2809643.82     10245343.81
      2809455.68     10245003.10
#Sta/Elev= 30
  4575.7 1049.56  4689.7 1041.29  4720.8 1038.42  4741.4 1037.46  4751.9 1036.16
  4820.8 1033.77  4834.9 1032.22  4876.3 1030.81  4886.7 1031.31  4917.8 1028.57
  4980.0 1024.97  4995.8 1022.95  4996.0 1022.45  4999.8 1022.95  5006.5 1023.37
  5012.2 1025.32  5066.1 1027.06  5087.9 1029.43  5125.7 1031.69  5131.4 1032.80
  5147.4 1032.98  5153.2 1034.13  5169.2 1034.50  5191.0 1036.94  5206.4 1037.50
  5240.7 1040.38  5272.3 1042.38  5315.9 1042.90  5337.6 1045.63  5389.2 1047.67
#Mann=3,-1,0
  4575.7    0.05       0  4995.8    0.05       0  4999.8    0.05       0
Bank Sta=4995.8,4999.8
Exp/Cntr=0.3,0.1

Type RM Length L Ch R = 1,2500,398,398,398
BEGIN DESCRIPTION:
SANFERNANDO069 5.0
END DESCRIPTION:
XS GIS Cut Line= 3
      2809955.68     10245653.15      2809983.06     10245406.76
      2809955.68     10245053.12
#Sta/Elev= 30
  4752.1 1041.36  4792.4 1038.97  4802.4 1037.95  4832.6 1035.94  4918.5 1033.42
  4943.3 1031.63  4963.4 1027.28  4973.5 1024.27  4978.5 1025.24  4983.5 1022.10
  4993.6 1019.16  4997.3 1018.77  4997.6 1018.27  5001.1 1018.27  5001.3 1018.77
  5004.3 1018.77  5013.7 1020.72  5023.7 1021.61  5029.8 1022.64  5053.8 1024.21
  5093.9 1025.67  5124.0 1028.05  5154.1 1029.73  5159.7 1030.66  5174.2 1031.79
  5214.3 1036.44  5244.4 1038.10  5274.5 1038.74  5314.6 1041.51  5354.7 1043.13
#Mann=4,-1,0
  4752.1    0.05       0  4918.5    0.12       0  4997.3    0.07       0
  5001.3    0.12       0
Bank Sta=4997.3,5001.3
Exp/Cntr=0.3,0.1

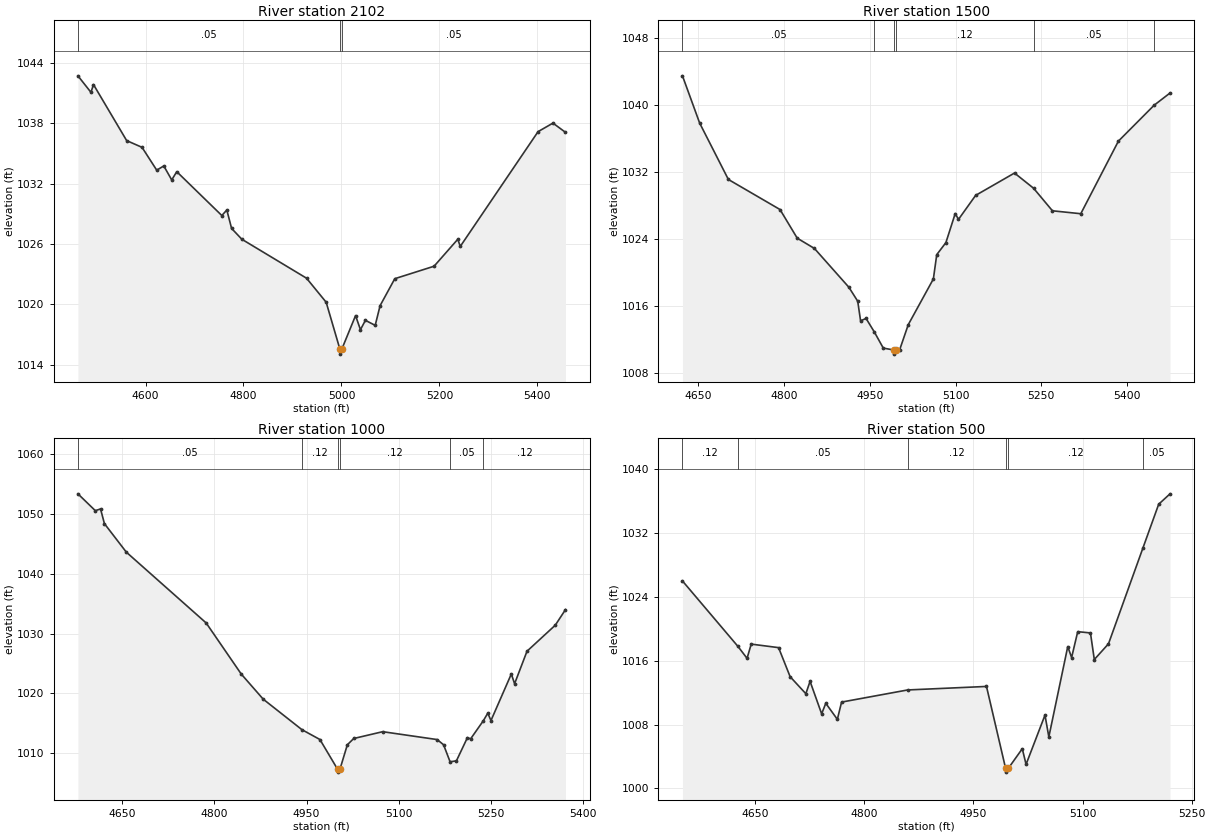
Type RM Length L Ch R = 1,2102,602,602,602
BEGIN DESCRIPTION:
Mapping XS 31ae1696
END DESCRIPTION:
XS GIS Cut Line= 4
      2810224.34     10245730.44      2810313.07     10245314.06
      2810299.42     10245020.54      2810258.51     10244747.76
#Sta/Elev= 30
  4462.0 1042.73  4488.6 1041.09  4493.8 1041.86  4561.5 1036.29  4592.9 1035.62
  4622.9 1033.35  4637.3 1033.77  4653.5 1032.38  4663.8 1033.20  4755.8 1028.84
  4766.0 1029.39  4775.7 1027.56  4796.7 1026.48  4928.7 1022.61  4968.8 1020.22
  4996.8 1015.56  4997.0 1015.06  5000.8 1015.56  5028.8 1018.89  5038.8 1017.49
  5048.9 1018.42  5068.9 1017.92  5078.9 1019.88  5108.9 1022.56  5189.1 1023.80
  5237.5 1026.48  5242.6 1025.77  5401.4 1037.18  5431.8 1038.03  5457.4 1037.11
#Mann=3,-1,0
  4462.0    0.05       0  4996.8    0.05       0  5000.8    0.05       0
Bank Sta=4996.8,5000.8
Exp/Cntr=0.3,0.1

Type RM Length L Ch R = 1,1500,500,500,500
BEGIN DESCRIPTION:
SANFERNANDO069 3.0
END DESCRIPTION:
XS GIS Cut Line= 3
      2810555.69     10245653.10      2810586.43     10245276.85
      2811005.67     10245053.12
#Sta/Elev= 30
  4622.5 1043.44  4652.6 1037.79  4702.8 1031.06  4793.1 1027.47  4823.2 1024.05
  4853.3 1022.82  4913.5 1018.19  4929.0 1016.52  4934.0 1014.18  4943.6 1014.46
  4958.1 1012.84  4973.7 1010.92  4991.7 1010.70  4992.0 1010.20  4995.7 1010.70
  5002.4 1010.73  5017.4 1013.72  5061.3 1019.18  5067.2 1022.08  5083.2 1023.52
  5099.5 1026.99  5105.2 1026.29  5135.2 1029.16  5203.2 1031.83  5236.6 1030.01
  5269.5 1027.32  5319.1 1026.97  5384.9 1035.64  5447.4 1039.93  5475.2 1041.39
#Mann=6,-1,0
  4622.5    0.05       0  4958.1    0.12       0  4991.7    0.07       0
  4995.7    0.12       0  5236.6    0.05       0  5447.4    0.12       0
Bank Sta=4991.7,4995.7
Exp/Cntr=0.3,0.1

Type RM Length L Ch R = 1,1000,500,500,500
BEGIN DESCRIPTION:
SANFERNANDO069 2.0
END DESCRIPTION:
XS GIS Cut Line= 3
      2810555.66     10245853.13      2810899.55     10245608.72
      2811005.68     10245253.12
#Sta/Elev= 30
  4578.1 1053.41  4606.4 1050.59  4614.9 1050.88  4621.2 1048.42  4656.8 1043.65
  4786.7 1031.79  4843.8 1023.23  4879.5 1019.03  4942.4 1013.93  4971.7 1012.28
  5000.3 1007.32  5000.6 1006.82  5004.3 1007.32  5016.3 1011.40  5026.7 1012.45
  5073.8 1013.59  5162.4 1012.27  5172.8 1011.40  5183.4 1008.55  5193.7 1008.71
  5211.6 1012.60  5216.8 1012.39  5237.5 1015.43  5244.7 1016.69  5249.9 1015.46
  5283.0 1023.25  5288.3 1021.62  5308.5 1027.06  5354.5 1031.42  5371.1 1034.03
#Mann=6,-1,0
  4578.1    0.05       0  4942.4    0.12       0  5000.3    0.07       0
  5004.3    0.12       0  5183.4    0.05       0  5237.5    0.12       0
Bank Sta=5000.3,5004.3
Exp/Cntr=0.3,0.1

Type RM Length L Ch R = 1,500,0,0,0
BEGIN DESCRIPTION:
SANFERNANDO069 1.0
END DESCRIPTION:
XS GIS Cut Line= 3
      2810905.69     10245803.10      2811127.20     10245411.40
      2811055.69     10245203.13
#Sta/Elev= 30
  4550.0 1025.98  4626.2 1017.79  4638.8 1016.29  4644.5 1018.07  4682.1 1017.63
  4698.0 1013.99  4719.6 1011.86  4725.4 1013.41  4741.3 1009.34  4747.0 1010.66
  4762.9 1008.65  4768.7 1010.81  4859.5 1012.33  4967.9 1012.77  4994.1 1002.54
  4994.4 1002.04  4998.1 1002.54  5017.1 1004.97  5022.3 1003.01  5048.3 1009.18
  5053.6 1006.45  5079.6 1017.76  5084.9 1016.39  5093.3 1019.63  5110.8 1019.47
  5116.1 1016.14  5135.6 1018.11  5183.1 1030.15  5204.6 1035.59  5220.2 1036.89
#Mann=6,-1,0
  4550.0    0.12       0  4626.2    0.05       0  4859.5    0.12       0
  4994.1    0.07       0  4998.1    0.12       0  5183.1    0.05       0
Bank Sta=4994.1,4998.1
Exp/Cntr=0.3,0.1

Chan Stop Cuts=-1