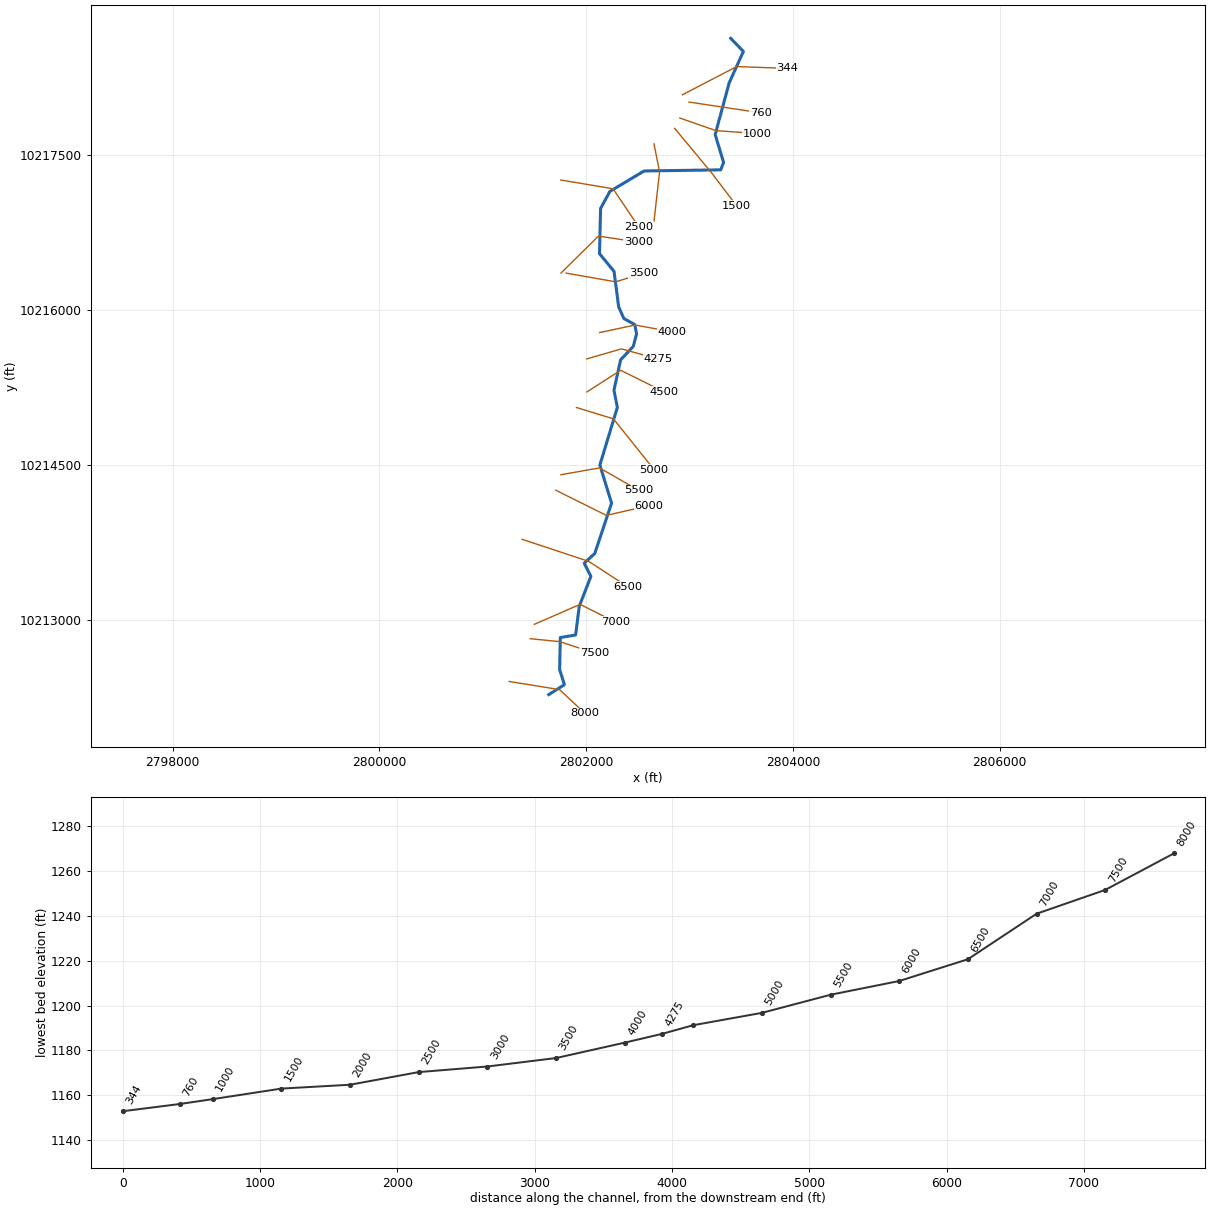
--- SANFERNANDO071.prj (project) ---

Proj Title=SANFERNANDO071 Base Level Engineering
Current Plan=p01
Default Exp/Contr=0.3,0.1
English Units
Geom File=g01
Flow File=f01
Plan File=p01
BEGIN DESCRIPTION:
SANFERNANDO071
END DESCRIPTION:

--- SANFERNANDO071.p01 (plan) ---

Plan Title=Multiple Run
Short Identifier=Multiple
Geom File=g01
Flow File=f01
Subcritical Flow
K Sum by GR= 0
Std Step Tol= 0.01
Critical Tol= 0.01
Num of Std Step Trials= 20
Max Error Tol= 0.3
Flow Tol Ratio= 0.001
Split Flow NTrial= 30
Split Flow Tol= 0.02
Split Flow Ratio= 0.02
Log Output Level= 0
Friction Slope Method= 1
Unsteady Friction Slope Method= 2
Unsteady Bridges Friction Slope Method= 1
Parabolic Critical Depth
Global Vel Dist=  1 , 1 , 1
Global Log Level= 0
CheckData=True
Encroach Param= -1, 0, 0, 0
BEGIN DESCRIPTION:
Multiple Run
END DESCRIPTION:

--- SANFERNANDO071.f01 (steady flow) ---

Flow Title=Multiple
Number of Profiles=7
Profile Names=10-year,25-year,50-year,1pct_min,100-year,1pct_plu,500-year
River Rch & RM= SANFERNANDO071,Reach-1,8000
     160     243     385     265     511     986     731
River Rch & RM= SANFERNANDO071,Reach-1,3500
     360     563    1227     845    1696    3404    2405
Boundary for River Rch & Prof#=SANFERNANDO071,Reach-1,1
Up Type=0
Dn Type=3
Dn Slope=0.005
Boundary for River Rch & Prof#=SANFERNANDO071,Reach-1,2
Up Type=0
Dn Type=3
Dn Slope=0.005
Boundary for River Rch & Prof#=SANFERNANDO071,Reach-1,3
Up Type=0
Dn Type=3
Dn Slope=0.005
Boundary for River Rch & Prof#=SANFERNANDO071,Reach-1,4
Up Type=0
Dn Type=3
Dn Slope=0.005
Boundary for River Rch & Prof#=SANFERNANDO071,Reach-1,5
Up Type=0
Dn Type=3
Dn Slope=0.005
Boundary for River Rch & Prof#=SANFERNANDO071,Reach-1,6
Up Type=0
Dn Type=3
Dn Slope=0.005
Boundary for River Rch & Prof#=SANFERNANDO071,Reach-1,7
Up Type=0
Dn Type=3
Dn Slope=0.005

--- SANFERNANDO071.g01 (geometry) ---

Geom Title=Existing Conditions

River Reach=SANFERNANDO071,Reach-1
Reach XY= 30
      2801637.75     10212276.00      2801789.00     10212372.00
      2801743.25     10212518.00      2801749.50     10212828.00
      2801897.50     10212853.00      2801932.75     10213130.00
      2802045.25     10213420.00      2801980.75     10213547.00
      2802082.75     10213641.00      2802245.25     10214128.00
      2802132.25     10214497.00      2802301.50     10215055.00
      2802268.25     10215220.00      2802332.75     10215514.00
      2802455.75     10215645.00      2802487.00     10215766.00
      2802470.25     10215855.00      2802364.00     10215914.00
      2802314.00     10216026.00      2802269.25     10216370.00
      2802128.75     10216541.00      2802139.00     10216978.00
      2802228.75     10217143.00      2802560.00     10217341.00
      2803301.25     10217352.00      2803328.75     10217424.00
      2803247.50     10217693.00      2803382.75     10218193.00
      2803520.25     10218497.00      2803398.00     10218624.00

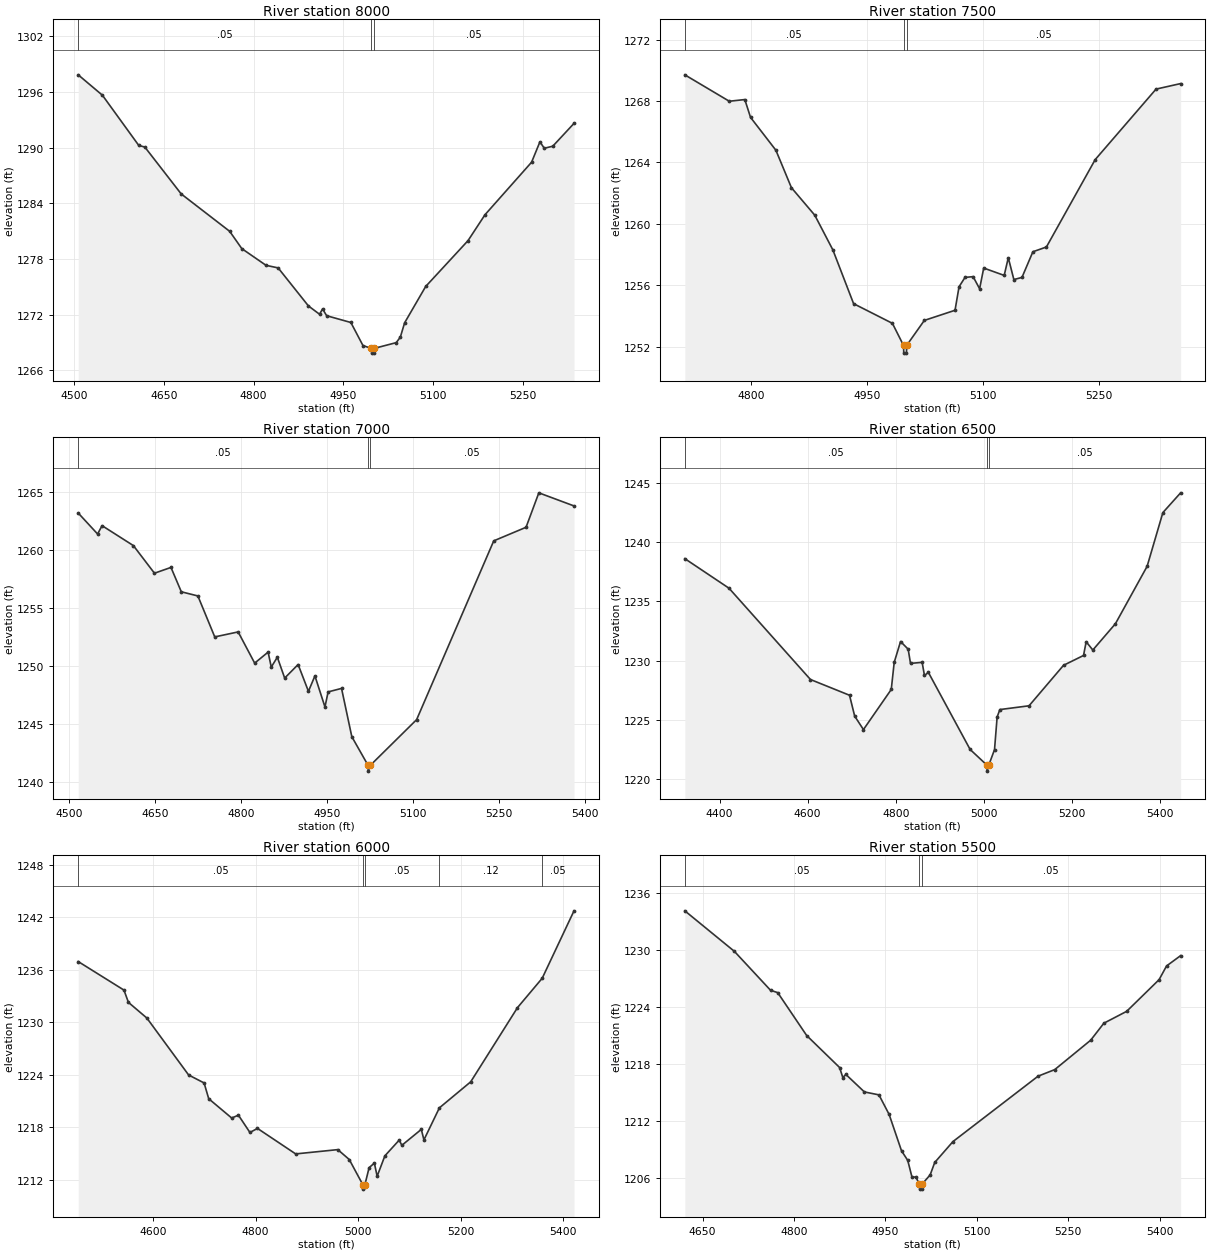
Type RM Length L Ch R = 1,8000,500,500,500
BEGIN DESCRIPTION:
SANFERNANDO071 16.0
END DESCRIPTION:
XS GIS Cut Line= 3
      2801255.67     10212403.11      2801742.63     10212324.30
      2801987.37     10212094.52
#Sta/Elev= 30
  4506.7 1297.84  4547.2 1295.64  4608.0 1290.23  4618.1 1290.06  4678.9 1285.01
  4760.0 1280.98  4780.2 1279.12  4820.7 1277.32  4841.0 1277.04  4891.7 1272.94
  4910.2 1272.05  4915.3 1272.62  4922.1 1271.89  4962.6 1271.16  4982.8 1268.68
  4997.0 1268.36  4997.3 1267.86  5000.8 1267.86  5001.0 1268.36  5038.4 1268.99
  5045.3 1269.58  5052.5 1271.13  5087.7 1275.04  5158.5 1279.98  5186.9 1282.77
  5264.8 1288.43  5278.7 1290.62  5286.0 1289.93  5300.2 1290.15  5335.7 1292.61
#Mann=3,-1,0
  4506.7    0.05       0  4997.0    0.03       0  5001.0    0.05       0
Bank Sta=4997,5001
Exp/Cntr=0.3,0.1

Type RM Length L Ch R = 1,7500,500,500,500
BEGIN DESCRIPTION:
SANFERNANDO071 15.0
END DESCRIPTION:
XS GIS Cut Line= 3
      2801458.42     10212816.64      2801743.25     10212788.69
      2802080.69     10212678.11
#Sta/Elev= 30
  4713.8 1269.70  4771.3 1267.98  4791.4 1268.09  4798.8 1266.93  4831.6 1264.79
  4851.7 1262.35  4881.9 1260.56  4905.3 1258.30  4932.1 1254.80  4982.3 1253.52
  4996.7 1252.08  4997.0 1251.58  5000.5 1251.58  5000.7 1252.08  5023.6 1253.71
  5063.3 1254.37  5068.5 1255.90  5076.2 1256.51  5086.7 1256.56  5095.1 1255.77
  5100.4 1257.12  5126.9 1256.64  5132.2 1257.79  5139.4 1256.37  5149.9 1256.51
  5164.0 1258.18  5181.5 1258.49  5244.6 1264.18  5323.3 1268.77  5355.1 1269.13
#Mann=3,-1,0
  4713.8    0.05       0  4996.7    0.03       0  5000.7    0.05       0
Bank Sta=4996.7,5000.7
Exp/Cntr=0.3,0.1

Type RM Length L Ch R = 1,7000,500,500,500
BEGIN DESCRIPTION:
SANFERNANDO071 14.0
END DESCRIPTION:
XS GIS Cut Line= 3
      2801497.54     10212955.54      2801941.01     10213149.17
      2802280.67     10212978.12
#Sta/Elev= 30
  4516.1 1263.20  4549.9 1261.39  4557.7 1262.11  4612.3 1260.39  4649.0 1258.01
  4677.8 1258.51  4695.8 1256.41  4724.7 1256.05  4754.1 1252.52  4794.9 1252.95
  4823.7 1250.26  4847.1 1251.21  4852.6 1249.92  4863.2 1250.77  4876.0 1248.97
  4899.4 1250.14  4917.4 1247.83  4928.7 1249.16  4946.2 1246.48  4951.7 1247.78
  4975.1 1248.08  4993.0 1243.92  5021.3 1241.45  5021.6 1240.95  5025.3 1241.45
  5106.0 1245.39  5240.4 1260.80  5296.7 1261.97  5319.0 1264.94  5380.3 1263.81
#Mann=3,-1,0
  4516.1    0.05       0  5021.3    0.03       0  5025.3    0.05       0
Bank Sta=5021.3,5025.3
Exp/Cntr=0.3,0.1

Type RM Length L Ch R = 1,6500,500,500,500
BEGIN DESCRIPTION:
SANFERNANDO071 13.0
END DESCRIPTION:
XS GIS Cut Line= 3
      2801380.68     10213778.11      2802025.22     10213564.55
      2802399.45     10213320.27
#Sta/Elev= 30
  4321.0 1238.61  4421.4 1236.11  4606.3 1228.40  4695.0 1227.07  4706.7 1225.31
  4726.6 1224.17  4789.8 1227.56  4796.5 1229.85  4810.9 1231.61  4828.2 1230.96
  4833.5 1229.76  4859.9 1229.85  4865.2 1228.74  4874.1 1229.00  4968.9 1222.49
  5007.2 1221.16  5007.4 1220.66  5011.2 1221.16  5024.3 1222.48  5030.2 1225.23
  5036.4 1225.86  5102.7 1226.18  5181.0 1229.60  5226.4 1230.43  5232.4 1231.59
  5247.5 1230.89  5298.8 1233.11  5370.8 1237.96  5406.6 1242.50  5446.9 1244.17
#Mann=3,-1,0
  4321.0    0.05       0  5007.2    0.05       0  5011.2    0.05       0
Bank Sta=5007.2,5011.2
Exp/Cntr=0.3,0.1

Type RM Length L Ch R = 1,6000,500,500,500
BEGIN DESCRIPTION:
SANFERNANDO071 12.0
END DESCRIPTION:
XS GIS Cut Line= 3
      2801705.70     10214253.11      2802194.60     10214009.80
      2802605.64     10214103.10
#Sta/Elev= 30
  4453.9 1236.94  4543.2 1233.68  4551.9 1232.28  4587.9 1230.49  4669.4 1223.99
  4699.6 1223.08  4708.6 1221.28  4753.4 1219.08  4766.6 1219.40  4789.0 1217.43
  4803.8 1217.89  4878.3 1214.98  4960.5 1215.47  4982.9 1214.34  5009.4 1211.46
  5009.6 1210.96  5013.4 1211.46  5021.6 1213.41  5031.9 1213.93  5037.3 1212.43
  5052.4 1214.76  5080.4 1216.56  5085.5 1215.96  5123.5 1217.78  5128.6 1216.58
  5158.8 1220.24  5219.9 1223.21  5311.2 1231.68  5359.4 1235.03  5421.5 1242.73
#Mann=5,-1,0
  4453.9    0.05       0  5009.4    0.03       0  5013.4    0.05       0
  5158.8    0.12       0  5359.4    0.05       0
Bank Sta=5009.4,5013.4
Exp/Cntr=0.3,0.1

Type RM Length L Ch R = 1,5500,500,500,500
BEGIN DESCRIPTION:
SANFERNANDO071 11.0
END DESCRIPTION:
XS GIS Cut Line= 3
      2801755.65     10214403.10      2802128.89     10214468.88
      2802505.69     10214253.11
#Sta/Elev= 30
  4621.0 1234.15  4702.3 1229.88  4761.6 1225.78  4773.4 1225.53  4820.9 1221.01
  4874.9 1217.64  4880.1 1216.59  4885.2 1216.91  4915.5 1215.07  4939.4 1214.76
  4956.1 1212.70  4976.4 1208.87  4986.6 1207.86  4993.6 1206.09  5000.0 1206.11
  5005.8 1205.33  5006.1 1204.83  5009.6 1204.83  5009.8 1205.33  5023.4 1206.33
  5030.9 1207.64  5060.8 1209.84  5200.4 1216.73  5227.7 1217.42  5286.7 1220.52
  5308.3 1222.31  5345.7 1223.56  5398.9 1226.90  5411.1 1228.34  5434.2 1229.43
#Mann=3,-1,0
  4621.0    0.05       0  5005.8    0.03       0  5009.8    0.05       0
Bank Sta=5005.8,5009.8
Exp/Cntr=0.3,0.1

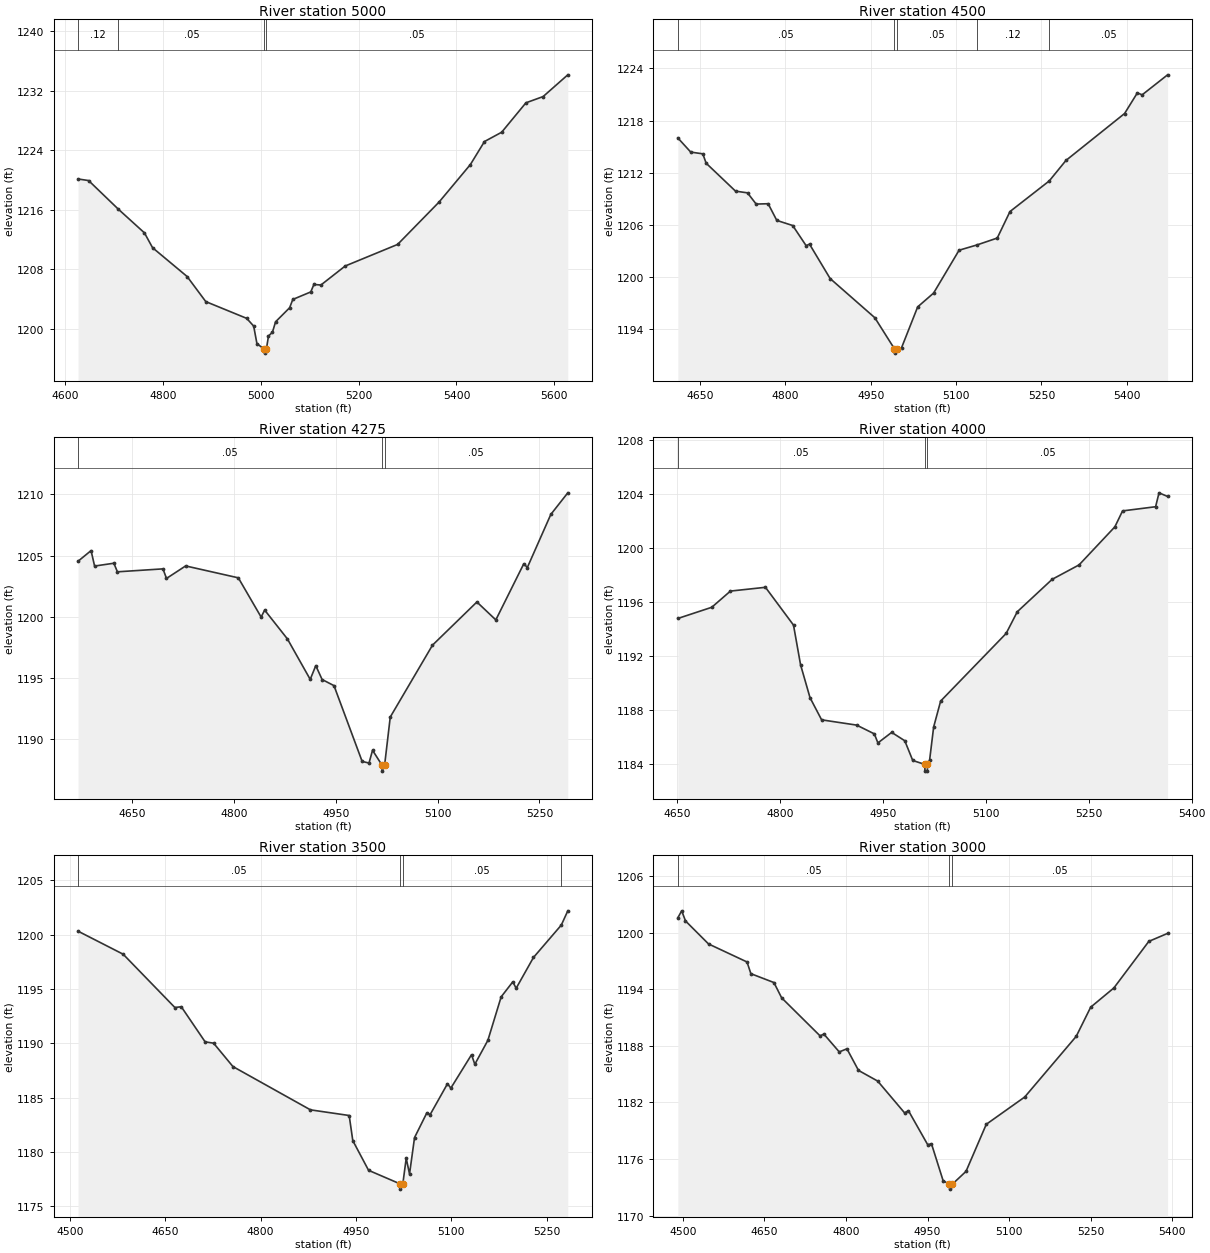
Type RM Length L Ch R = 1,5000,500,500,500
BEGIN DESCRIPTION:
SANFERNANDO071 10.0
END DESCRIPTION:
XS GIS Cut Line= 3
      2801905.73     10215053.10      2802263.58     10214943.35
      2802655.71     10214453.08
#Sta/Elev= 30
  4625.7 1220.14  4647.3 1219.93  4708.4 1216.07  4761.6 1212.90  4778.2 1210.91
  4848.9 1207.04  4887.1 1203.67  4970.8 1201.42  4985.1 1200.38  4991.7 1198.04
  5007.0 1197.25  5007.3 1196.75  5011.0 1197.25  5015.4 1199.05  5023.5 1199.56
  5029.9 1200.96  5058.7 1202.85  5065.1 1203.96  5101.9 1204.97  5108.3 1205.97
  5122.7 1205.90  5172.3 1208.45  5279.6 1211.35  5364.4 1217.04  5428.5 1222.08
  5457.3 1225.17  5492.5 1226.42  5542.1 1230.37  5577.3 1231.21  5627.8 1234.13
#Mann=4,-1,0
  4625.7    0.12       0  4708.4    0.05       0  5007.0    0.05       0
  5011.0    0.05       0
Bank Sta=5007,5011
Exp/Cntr=0.3,0.1

Type RM Length L Ch R = 1,4500,225,225,225
BEGIN DESCRIPTION:
SANFERNANDO071 9.0
END DESCRIPTION:
XS GIS Cut Line= 3
      2802005.73     10215203.14      2802333.23     10215413.42
      2802755.67     10215203.12
#Sta/Elev= 30
  4610.8 1216.01  4633.5 1214.38  4654.7 1214.18  4660.6 1213.10  4712.2 1209.89
  4733.3 1209.69  4748.5 1208.40  4769.6 1208.44  4784.8 1206.52  4812.8 1205.93
  4836.4 1203.61  4842.3 1203.79  4878.6 1199.83  4957.2 1195.32  4991.6 1191.75
  4991.8 1191.25  4995.6 1191.75  5004.2 1191.88  5032.5 1196.57  5060.5 1198.16
  5105.3 1203.09  5136.4 1203.69  5172.4 1204.49  5194.8 1207.54  5263.8 1211.06
  5293.2 1213.42  5396.3 1218.82  5418.7 1221.19  5427.2 1220.97  5471.9 1223.27
#Mann=5,-1,0
  4610.8    0.05       0  4991.6    0.05       0  4995.6    0.05       0
  5136.4    0.12       0  5263.8    0.05       0
Bank Sta=4991.6,4995.6
Exp/Cntr=0.3,0.1

Type RM Length L Ch R = 1,4275,275,275,275
BEGIN DESCRIPTION:
Mapping XS fbe85b04
END DESCRIPTION:
XS GIS Cut Line= 3
      2802003.50     10215522.40      2802339.83     10215620.04
      2802697.93     10215522.37
#Sta/Elev= 30
  4570.4 1204.53  4589.6 1205.40  4594.8 1204.14  4623.2 1204.37  4628.4 1203.67
  4695.5 1203.91  4700.7 1203.13  4728.9 1204.15  4806.5 1203.18  4840.1 1199.98
  4845.3 1200.55  4878.8 1198.20  4912.4 1194.90  4920.6 1196.02  4929.9 1194.89
  4947.4 1194.39  4988.9 1188.21  4999.0 1188.08  5004.2 1189.12  5018.0 1187.92
  5018.2 1187.42  5022.0 1187.92  5030.3 1191.83  5092.5 1197.69  5157.9 1201.21
  5185.8 1199.75  5227.0 1204.33  5232.2 1204.02  5266.8 1208.35  5291.8 1210.11
#Mann=3,-1,0
  4570.4    0.05       0  5018.0    0.05       0  5022.0    0.05       0
Bank Sta=5018,5022
Exp/Cntr=0.3,0.1

Type RM Length L Ch R = 1,4000,500,500,500
BEGIN DESCRIPTION:
SANFERNANDO071 8.0
END DESCRIPTION:
XS GIS Cut Line= 3
      2802130.67     10215778.11      2802472.34     10215851.17
      2802831.30     10215785.57
#Sta/Elev= 30
  4650.6 1194.77  4700.1 1195.60  4727.3 1196.80  4778.4 1197.08  4819.3 1194.28
  4829.6 1191.34  4843.4 1188.90  4860.3 1187.26  4911.4 1186.87  4937.2 1186.22
  4942.4 1185.55  4962.5 1186.33  4981.6 1185.71  4993.2 1184.25  5010.7 1183.96
  5011.0 1183.46  5014.5 1183.46  5014.7 1183.96  5017.8 1184.27  5023.7 1186.73
  5033.9 1188.65  5129.4 1193.66  5145.7 1195.27  5196.5 1197.67  5235.8 1198.74
  5288.0 1201.56  5299.2 1202.74  5347.4 1203.05  5352.4 1204.08  5364.9 1203.81
#Mann=3,-1,0
  4650.6    0.05       0  5010.7    0.05       0  5014.7    0.05       0
Bank Sta=5010.7,5014.7
Exp/Cntr=0.3,0.1

Type RM Length L Ch R = 1,3500,500,500,500
BEGIN DESCRIPTION:
SANFERNANDO071 7.0
END DESCRIPTION:
XS GIS Cut Line= 3
      2801805.73     10216353.10      2802285.36     10216268.69
      2802555.68     10216353.11
#Sta/Elev= 30
  4513.0 1200.31  4584.0 1198.19  4665.3 1193.29  4675.4 1193.36  4712.9 1190.13
  4726.2 1190.01  4756.6 1187.86  4878.5 1183.88  4939.4 1183.36  4945.1 1181.05
  4969.9 1178.32  5018.8 1177.09  5019.2 1176.59  5023.8 1177.09  5029.1 1179.43
  5034.3 1177.98  5042.2 1181.33  5061.6 1183.61  5066.8 1183.45  5094.0 1186.28
  5099.3 1185.88  5131.8 1188.95  5137.0 1188.07  5157.5 1190.27  5178.4 1194.27
  5196.7 1195.65  5202.0 1195.06  5229.2 1197.89  5273.0 1200.87  5283.2 1202.18
#Mann=4,-1,0
  4513.0    0.05       0  5018.8    0.03       0  5023.8    0.05       0
  5273.0    0.05       0
Bank Sta=5018.8,5023.8
Exp/Cntr=0.3,0.1

Type RM Length L Ch R = 1,3000,500,500,500
BEGIN DESCRIPTION:
SANFERNANDO071 6.0
END DESCRIPTION:
XS GIS Cut Line= 3
      2801755.67     10216353.09      2802118.25     10216710.90
      2802505.66     10216653.11
#Sta/Elev= 30
  4490.6 1201.57  4497.7 1202.31  4504.7 1201.24  4547.1 1198.80  4617.9 1196.89
  4625.0 1195.65  4667.4 1194.71  4681.6 1193.09  4752.3 1189.06  4759.3 1189.25
  4787.6 1187.36  4801.7 1187.69  4823.0 1185.40  4858.3 1184.27  4907.8 1180.90
  4914.9 1181.13  4950.3 1177.53  4957.3 1177.62  4978.6 1173.73  4990.2 1173.32
  4990.6 1172.82  4995.2 1173.32  5020.8 1174.70  5058.1 1179.69  5128.8 1182.58
  5223.6 1189.01  5250.2 1192.10  5292.9 1194.14  5357.1 1199.07  5391.7 1199.92
#Mann=3,-1,0
  4490.6    0.05       0  4990.2    0.03       0  4995.2    0.05       0
Bank Sta=4990.2,4995.2
Exp/Cntr=0.3,0.1

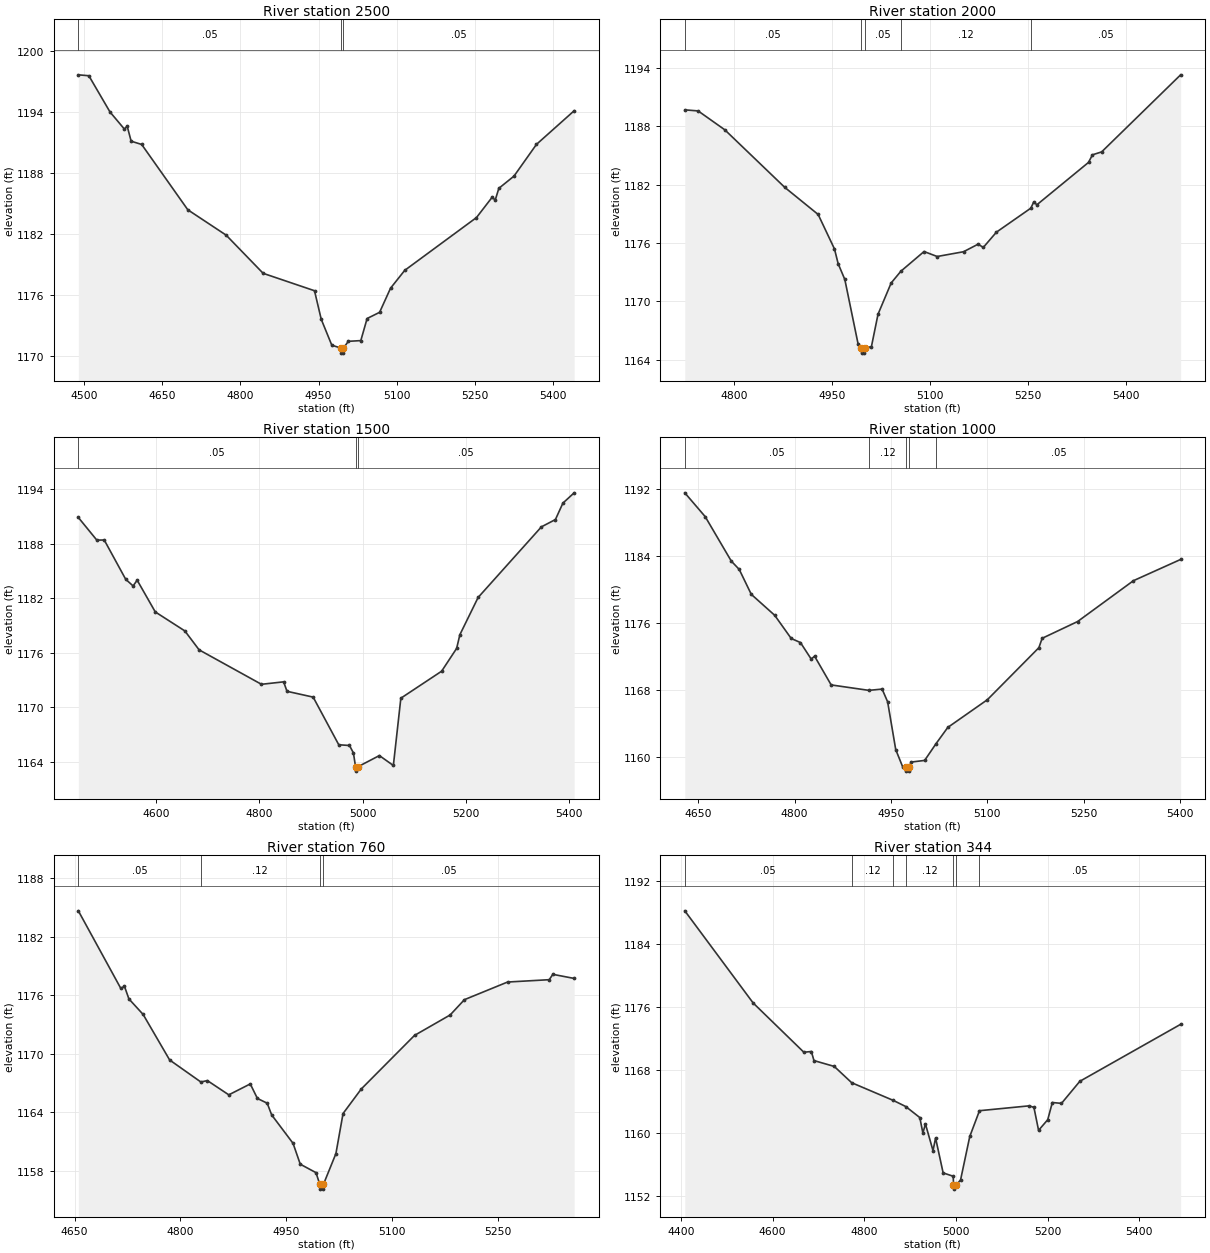
Type RM Length L Ch R = 1,2500,500,500,500
BEGIN DESCRIPTION:
SANFERNANDO071 5.0
END DESCRIPTION:
XS GIS Cut Line= 3
      2801755.71     10217253.11      2802259.84     10217168.98
      2802505.69     10216803.10
#Sta/Elev= 30
  4488.9 1197.67  4509.1 1197.58  4549.7 1194.02  4577.5 1192.33  4582.6 1192.64
  4590.3 1191.15  4610.5 1190.83  4699.1 1184.41  4772.7 1181.92  4843.7 1178.17
  4942.3 1176.46  4955.2 1173.66  4975.5 1171.11  4992.8 1170.83  4993.2 1170.33
  4997.5 1170.33  4997.9 1170.83  5007.3 1171.49  5031.2 1171.56  5043.3 1173.73
  5067.3 1174.34  5088.3 1176.71  5115.5 1178.46  5253.3 1183.65  5283.3 1185.64
  5289.3 1185.37  5296.2 1186.52  5325.3 1187.72  5368.5 1190.84  5440.8 1194.14
#Mann=3,-1,0
  4488.9    0.05       0  4992.8    0.03       0  4997.9    0.05       0
Bank Sta=4992.8,4997.9
Exp/Cntr=0.3,0.1

Type RM Length L Ch R = 1,2000,500,500,500
BEGIN DESCRIPTION:
SANFERNANDO071 4.0
END DESCRIPTION:
XS GIS Cut Line= 3
      2802655.68     10217603.15      2802709.85     10217333.43
      2802655.68     10216853.08
#Sta/Elev= 30
  4724.9 1189.69  4745.3 1189.58  4786.1 1187.64  4877.9 1181.72  4928.9 1178.94
  4953.9 1175.39  4959.5 1173.88  4969.7 1172.26  4990.1 1165.60  4995.1 1165.19
  4995.5 1164.69  4999.8 1164.69  5000.2 1165.19  5010.4 1165.36  5020.5 1168.69
  5040.6 1171.90  5055.5 1173.11  5090.9 1175.13  5111.0 1174.62  5151.3 1175.11
  5173.7 1175.89  5181.5 1175.55  5201.6 1177.12  5254.3 1179.59  5258.6 1180.21
  5263.6 1179.94  5342.5 1184.29  5348.5 1185.07  5362.6 1185.37  5483.4 1193.29
#Mann=5,-1,0
  4724.9    0.05       0  4995.1    0.05       0  5000.2    0.05       0
  5055.5    0.12       0  5254.3    0.05       0
Bank Sta=4995.1,5000.2
Exp/Cntr=0.3,0.1

Type RM Length L Ch R = 1,1500,500,500,500
BEGIN DESCRIPTION:
SANFERNANDO071 3.0
END DESCRIPTION:
XS GIS Cut Line= 3
      2802855.67     10217753.13      2803207.62     10217329.45
      2803455.67     10217003.13
#Sta/Elev= 30
  4449.2 1190.87  4485.0 1188.38  4499.4 1188.39  4541.0 1184.07  4555.3 1183.34
  4563.2 1183.97  4598.3 1180.48  4655.6 1178.39  4683.2 1176.31  4804.0 1172.52
  4847.0 1172.79  4853.5 1171.75  4904.2 1171.11  4953.8 1165.87  4974.6 1165.79
  4982.2 1164.97  4986.3 1163.47  4986.7 1162.97  4991.5 1163.47  5032.5 1164.68
  5059.6 1163.59  5074.1 1170.99  5153.1 1173.96  5182.2 1176.47  5188.5 1177.98
  5223.8 1182.07  5346.5 1189.84  5373.6 1190.64  5388.1 1192.45  5409.9 1193.58
#Mann=3,-1,0
  4449.2    0.05       0  4986.3    0.03       0  4991.5    0.05       0
Bank Sta=4986.3,4991.5
Exp/Cntr=0.3,0.1

Type RM Length L Ch R = 1,1000,240,240,240
BEGIN DESCRIPTION:
SANFERNANDO071 2.0
END DESCRIPTION:
XS GIS Cut Line= 3
      2802905.67     10217853.12      2803256.00     10217731.02
      2803655.73     10217703.11
#Sta/Elev= 30
  4629.0 1191.52  4660.8 1188.67  4701.4 1183.36  4713.7 1182.37  4732.5 1179.39
  4768.9 1176.89  4794.6 1174.12  4809.0 1173.63  4825.7 1171.66  4831.0 1172.00
  4856.8 1168.57  4915.4 1167.92  4936.1 1168.07  4944.7 1166.55  4957.3 1160.84
  4967.9 1158.82  4973.2 1158.77  4973.6 1158.27  4978.1 1158.27  4978.5 1158.77
  4981.1 1159.35  5002.3 1159.55  5020.2 1161.57  5038.3 1163.49  5099.9 1166.80
  5180.1 1173.02  5185.2 1174.14  5240.3 1176.14  5327.2 1181.02  5400.7 1183.56
#Mann=5,-1,0
  4629.0    0.05       0  4915.4    0.12       0  4973.2    0.07       0
  4978.5    0.12       0  5020.2    0.05       0
Bank Sta=4973.2,4978.5
Exp/Cntr=0.3,0.1

Type RM Length L Ch R = 1,760,416,416,416
BEGIN DESCRIPTION:
Mapping XS 6e58ede7
END DESCRIPTION:
XS GIS Cut Line= 2
      2802994.90     10218007.61      2803689.33     10217903.45
#Sta/Elev= 30
  4655.4 1184.67  4715.6 1176.70  4720.7 1176.93  4727.0 1175.63  4747.2 1174.03
  4784.7 1169.36  4828.9 1167.10  4838.2 1167.24  4868.5 1165.78  4898.9 1166.90
  4909.0 1165.41  4922.9 1164.92  4929.2 1163.72  4959.5 1160.80  4969.7 1158.66
  4992.0 1157.79  4997.3 1156.60  4997.7 1156.10  5002.2 1156.10  5002.6 1156.60
  5020.2 1159.75  5030.3 1163.86  5056.1 1166.38  5131.5 1171.88  5182.0 1173.98
  5202.2 1175.55  5263.3 1177.36  5322.3 1177.60  5327.4 1178.15  5357.6 1177.73
#Mann=4,-1,0
  4655.4    0.05       0  4828.9    0.12       0  4997.3    0.05       0
  5002.6    0.05       0
Bank Sta=4997.3,5002.6
Exp/Cntr=0.3,0.1

Type RM Length L Ch R = 1,344,0,0,0
BEGIN DESCRIPTION:
SANFERNANDO071 1.0
END DESCRIPTION:
XS GIS Cut Line= 3
      2802930.72     10218078.13      2803455.75     10218351.00
      2803945.42     10218333.13
#Sta/Elev= 30
  4408.3 1188.18  4557.4 1176.49  4668.0 1170.24  4684.4 1170.33  4690.1 1169.18
  4734.3 1168.44  4772.4 1166.37  4863.4 1164.12  4890.3 1163.35  4921.0 1161.95
  4927.7 1159.99  4933.3 1161.14  4949.8 1157.75  4955.4 1159.36  4971.9 1154.93
  4994.0 1154.50  4994.5 1153.37  4994.9 1152.87  4999.8 1153.37  5009.9 1154.03
  5030.0 1159.55  5051.2 1162.82  5160.0 1163.44  5170.0 1163.23  5180.1 1160.33
  5200.1 1161.68  5210.1 1163.86  5230.1 1163.75  5270.1 1166.55  5490.0 1173.78
#Mann=7,-1,0
  4408.3    0.05       0  4772.4    0.12       0  4863.4    0.05       0
  4890.3    0.12       0  4994.5    0.07       0  4999.8    0.12       0
  5051.2    0.05       0
Bank Sta=4994.5,4999.8
Exp/Cntr=0.3,0.1

Chan Stop Cuts=-1