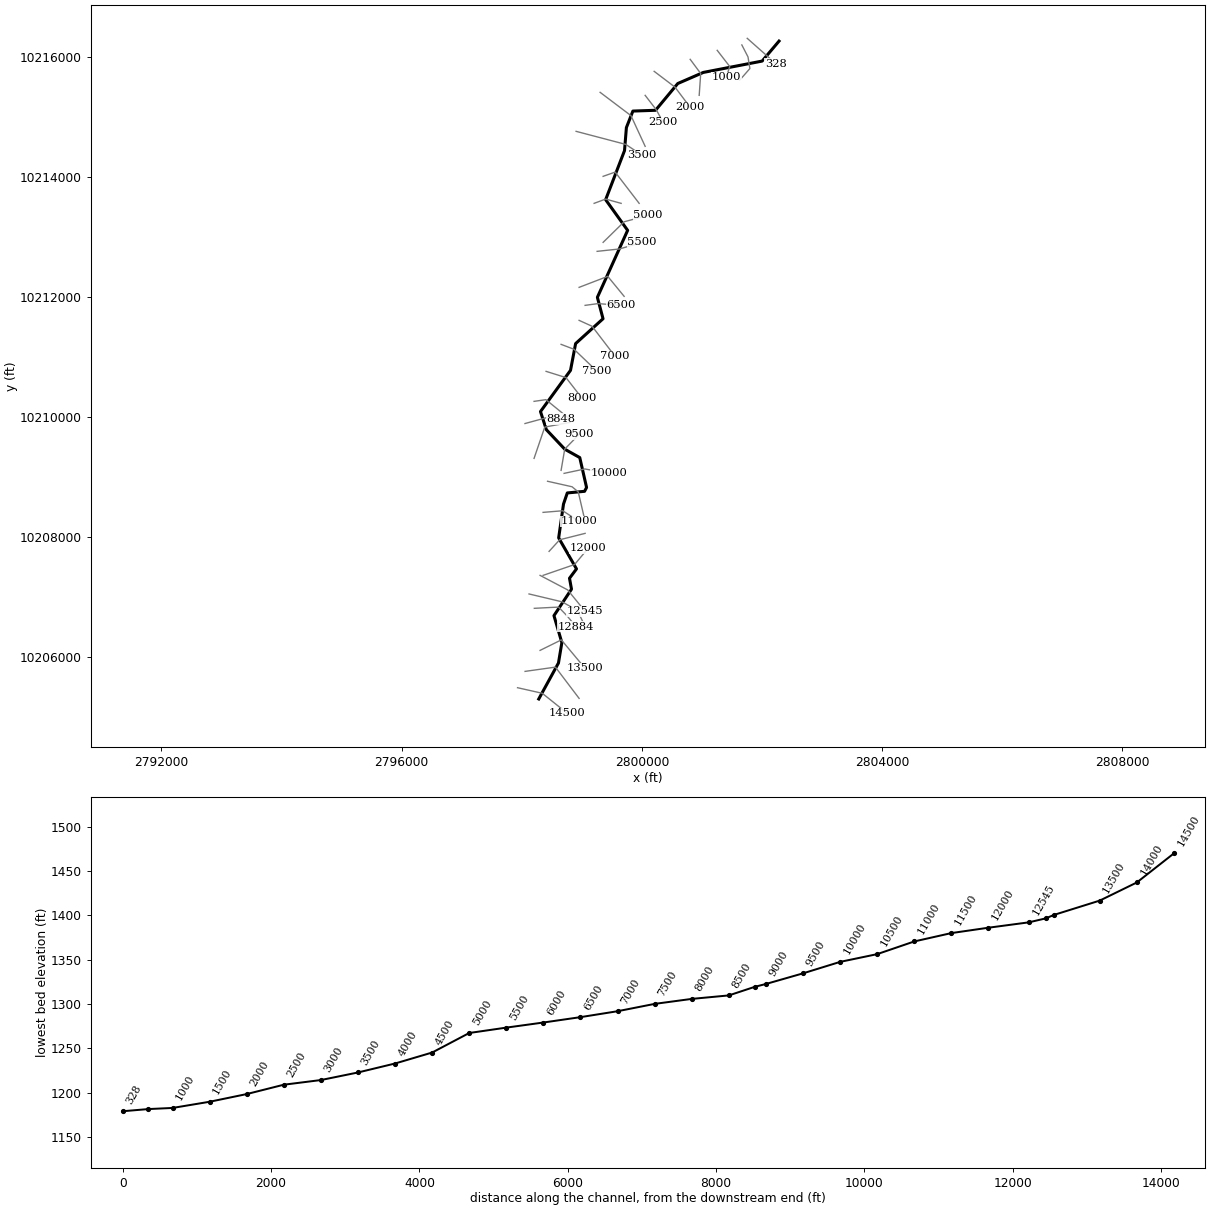
--- SANFERNANDO072.prj (project) ---

Proj Title=SANFERNANDO072 Base Level Engineering
Current Plan=p01
Default Exp/Contr=0.3,0.1
English Units
Geom File=g01
Flow File=f01
Plan File=p01
BEGIN DESCRIPTION:
SANFERNANDO072
END DESCRIPTION:

--- SANFERNANDO072.p01 (plan) ---

Plan Title=Multiple Run
Short Identifier=Multiple
Geom File=g01
Flow File=f01
Subcritical Flow
K Sum by GR= 0
Std Step Tol= 0.01
Critical Tol= 0.01
Num of Std Step Trials= 20
Max Error Tol= 0.3
Flow Tol Ratio= 0.001
Split Flow NTrial= 30
Split Flow Tol= 0.02
Split Flow Ratio= 0.02
Log Output Level= 0
Friction Slope Method= 1
Unsteady Friction Slope Method= 2
Unsteady Bridges Friction Slope Method= 1
Parabolic Critical Depth
Global Vel Dist=  1 , 1 , 1
Global Log Level= 0
CheckData=True
Encroach Param= -1, 0, 0, 0
BEGIN DESCRIPTION:
Multiple Run
END DESCRIPTION:

--- SANFERNANDO072.f01 (steady flow) ---

Flow Title=Multiple
Number of Profiles=7
Profile Names=10-year,25-year,50-year,1pct_min,100-year,1pct_plu,500-year
River Rch & RM= SANFERNANDO072,Reach-1,14500
     460     750    1420    1001    1983    3929    2863
River Rch & RM= SANFERNANDO072,Reach-1,3000
     571     947    1770    1282    2488    4831    3591
River Rch & RM= SANFERNANDO072,Reach-1,328
     360     563    1227     845    1696    3404    2405
Boundary for River Rch & Prof#=SANFERNANDO072,Reach-1,1
Up Type=0
Dn Type=3
Dn Slope=0.005
Boundary for River Rch & Prof#=SANFERNANDO072,Reach-1,2
Up Type=0
Dn Type=3
Dn Slope=0.005
Boundary for River Rch & Prof#=SANFERNANDO072,Reach-1,3
Up Type=0
Dn Type=3
Dn Slope=0.005
Boundary for River Rch & Prof#=SANFERNANDO072,Reach-1,4
Up Type=0
Dn Type=3
Dn Slope=0.005
Boundary for River Rch & Prof#=SANFERNANDO072,Reach-1,5
Up Type=0
Dn Type=3
Dn Slope=0.005
Boundary for River Rch & Prof#=SANFERNANDO072,Reach-1,6
Up Type=0
Dn Type=3
Dn Slope=0.005
Boundary for River Rch & Prof#=SANFERNANDO072,Reach-1,7
Up Type=0
Dn Type=3
Dn Slope=0.005

--- SANFERNANDO072.g01 (geometry) ---

Geom Title=Existing Conditions

River Reach=SANFERNANDO072,Reach-1
Reach XY= 30
      2798283.50     10205293.00      2798612.00     10205893.00
      2798668.25     10206232.00      2798537.00     10206682.00
      2798829.00     10207123.00      2798795.75     10207305.00
      2798912.25     10207461.00      2798615.25     10207978.00
      2798695.75     10208541.00      2798759.00     10208727.00
      2799046.50     10208754.00      2799080.00     10208818.00
      2798966.75     10209316.00      2798716.75     10209456.00
      2798410.50     10209781.00      2798312.50     10210083.00
      2798812.50     10210770.00      2798897.50     10211216.00
      2799354.25     10211630.00      2799260.00     10211987.00
      2799764.00     10213103.00      2799397.50     10213614.00
      2799712.00     10214432.00      2799743.25     10214816.00
      2799851.50     10215091.00      2800228.50     10215104.00
      2800599.00     10215550.00      2801024.50     10215735.00
      2802003.75     10215924.00      2802285.25     10216257.00

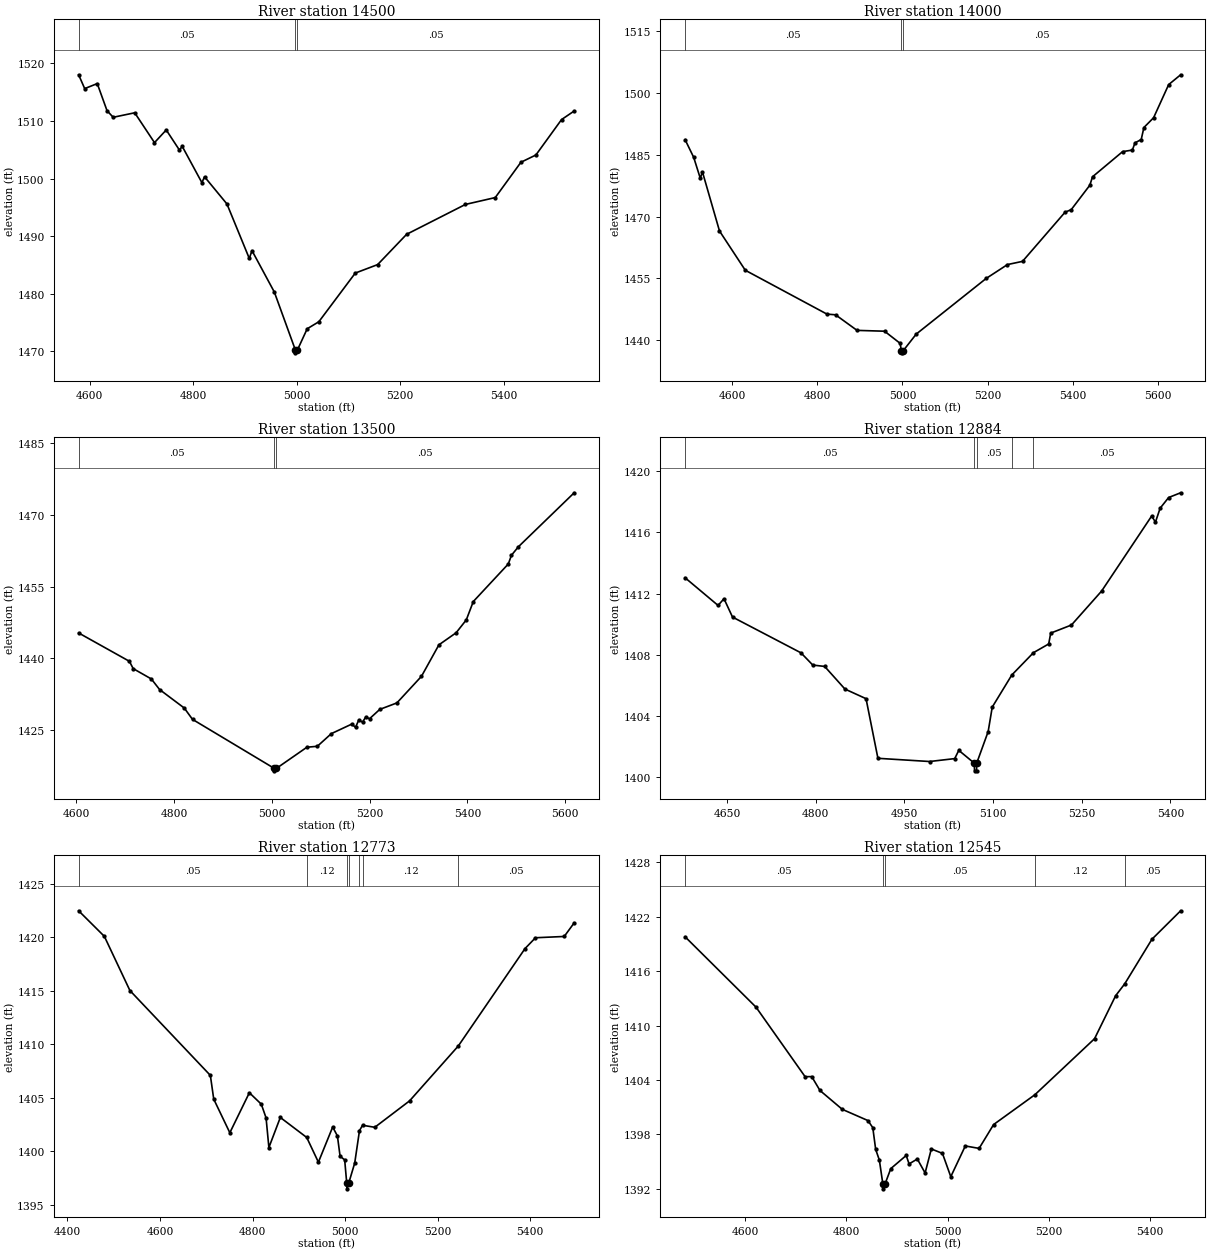
Type RM Length L Ch R = 1,14500,500,500,500
BEGIN DESCRIPTION:
SANFERNANDO072 29.0
END DESCRIPTION:
XS GIS Cut Line= 3
      2797930.52     10205480.95      2798341.33     10205388.43
      2798760.25     10205053.26
#Sta/Elev= 30
  4578.9 1518.01  4590.6 1515.61  4614.9 1516.48  4633.8 1511.77  4645.7 1510.63
  4687.3 1511.41  4725.5 1506.23  4748.2 1508.43  4773.8 1504.92  4779.0 1505.60
  4817.1 1499.28  4822.2 1500.30  4865.5 1495.58  4908.7 1486.12  4913.9 1487.48
  4957.1 1480.28  4997.7 1470.23  4997.9 1469.73  5001.7 1470.23  5020.6 1473.91
  5043.1 1475.13  5113.5 1483.58  5156.7 1485.05  5212.7 1490.31  5326.4 1495.50
  5384.0 1496.69  5433.6 1502.82  5462.5 1504.08  5512.1 1510.23  5536.5 1511.72
#Mann=3,-1,0
  4578.9    0.05       0  4997.7    0.05       0  5001.7    0.05       0
Bank Sta=4997.7,5001.7
Exp/Cntr=0.3,0.1

Type RM Length L Ch R = 1,14000,500,500,500
BEGIN DESCRIPTION:
SANFERNANDO072 28.0
END DESCRIPTION:
XS GIS Cut Line= 3
      2798055.68     10205753.11      2798561.22     10205824.10
      2798955.70     10205303.09
#Sta/Elev= 30
  4489.5 1488.67  4509.7 1484.38  4525.2 1479.30  4530.2 1480.87  4570.3 1466.51
  4630.9 1456.98  4822.7 1446.34  4842.9 1446.17  4893.4 1442.39  4958.0 1442.19
  4994.4 1439.26  4997.7 1437.44  4998.0 1436.94  5001.7 1437.44  5032.4 1441.49
  5196.8 1455.00  5246.7 1458.36  5282.1 1459.14  5382.0 1471.07  5396.5 1471.69
  5440.2 1477.62  5446.5 1479.66  5517.2 1485.77  5540.1 1486.15  5546.3 1487.90
  5560.9 1488.71  5567.2 1491.62  5590.0 1494.00  5625.4 1502.04  5653.5 1504.42
#Mann=3,-1,0
  4489.5    0.05       0  4997.7    0.03       0  5001.7    0.05       0
Bank Sta=4997.7,5001.7
Exp/Cntr=0.3,0.1

Type RM Length L Ch R = 1,13500,616,616,616
BEGIN DESCRIPTION:
SANFERNANDO072 27.0
END DESCRIPTION:
XS GIS Cut Line= 3
      2798305.65     10206103.10      2798659.98     10206278.12
      2799055.66     10205803.14
#Sta/Elev= 30
  4604.8 1445.30  4708.6 1439.38  4716.4 1437.85  4753.5 1435.69  4770.4 1433.48
  4820.8 1429.62  4837.7 1427.25  5005.1 1417.00  5005.3 1416.50  5009.1 1417.00
  5071.6 1421.43  5093.0 1421.63  5121.6 1424.27  5163.3 1426.26  5171.1 1425.59
  5177.6 1427.10  5185.4 1426.68  5191.9 1427.73  5199.7 1427.38  5220.6 1429.33
  5255.7 1430.69  5305.9 1436.24  5341.6 1442.82  5376.8 1445.34  5397.6 1448.03
  5411.9 1451.86  5483.5 1459.71  5490.0 1461.54  5504.3 1463.32  5618.2 1474.58
#Mann=3,-1,0
  4604.8    0.05       0  5005.1    0.03       0  5009.1    0.05       0
Bank Sta=5005.1,5009.1
Exp/Cntr=0.3,0.1

Type RM Length L Ch R = 1,12884,111,111,111
BEGIN DESCRIPTION:
Mapping XS 5681fd79
END DESCRIPTION:
XS GIS Cut Line= 5
      2798209.94     10206803.94      2798480.84     10206818.19
      2798614.85     10206823.90      2798760.26     10206672.78
      2798901.74     10206500.17
#Sta/Elev= 30
  4579.1 1413.03  4634.9 1411.22  4644.9 1411.66  4659.3 1410.46  4775.1 1408.12
  4795.1 1407.32  4815.2 1407.23  4849.5 1405.75  4885.2 1405.12  4905.3 1401.22
  4992.7 1401.01  5035.2 1401.20  5042.1 1401.74  5068.4 1400.90  5068.7 1400.40
  5072.2 1400.40  5072.4 1400.90  5091.8 1402.97  5098.7 1404.57  5131.8 1406.67
  5168.4 1408.13  5194.2 1408.70  5197.6 1409.41  5232.7 1409.94  5283.7 1412.16
  5368.4 1417.07  5374.8 1416.67  5382.7 1417.58  5397.1 1418.28  5417.4 1418.59
#Mann=5,-1,0
  4579.1    0.05       0  5068.4    0.05       0  5072.4    0.05       0
  5131.8    0.12       0  5168.4    0.05       0
Bank Sta=5068.4,5072.4
Exp/Cntr=0.3,0.1

Type RM Length L Ch R = 1,12773,228,228,228
BEGIN DESCRIPTION:
Mapping XS 1fbba8c2
END DESCRIPTION:
XS GIS Cut Line= 5
      2798121.59     10207043.44      2798529.31     10206946.50
      2798671.87     10206912.29      2798925.64     10206769.72
      2799019.17     10206576.99
#Sta/Elev= 30
  4424.2 1422.46  4479.8 1420.07  4535.0 1415.01  4708.9 1407.08  4716.2 1404.86
  4751.0 1401.72  4793.2 1405.46  4819.0 1404.39  4829.3 1403.11  4835.4 1400.34
  4860.1 1403.15  4917.2 1401.28  4942.4 1398.97  4973.3 1402.26  4983.5 1401.42
  4989.3 1399.52  4999.2 1399.19  5003.7 1396.98  5004.0 1396.48  5007.7 1396.98
  5020.9 1398.89  5031.2 1401.92  5037.9 1402.42  5064.3 1402.23  5139.5 1404.70
  5244.8 1409.83  5389.0 1418.93  5411.6 1419.94  5473.7 1420.06  5495.2 1421.33
#Mann=7,-1,0
  4424.2    0.05       0  4917.2    0.12       0  5003.7    0.07       0
  5007.7    0.12       0  5031.2    0.05       0  5037.9    0.12       0
  5244.8    0.05       0
Bank Sta=5003.7,5007.7
Exp/Cntr=0.3,0.1

Type RM Length L Ch R = 1,12545,545,545,545
BEGIN DESCRIPTION:
SANFERNANDO072 25.0
END DESCRIPTION:
XS GIS Cut Line= 3
      2798305.70     10207353.10      2798765.00     10207111.00
      2799055.71     10206753.08
#Sta/Elev= 30
  4480.8 1419.80  4621.1 1412.04  4718.2 1404.37  4731.3 1404.38  4747.6 1402.85
  4791.7 1400.77  4842.5 1399.53  4852.1 1398.75  4857.8 1396.35  4865.1 1395.17
  4872.1 1392.50  4872.4 1392.00  4876.1 1392.50  4887.7 1394.23  4918.2 1395.68
  4923.9 1394.75  4940.2 1395.29  4955.6 1393.75  4967.9 1396.40  4989.9 1395.91
  5006.4 1393.34  5035.1 1396.73  5062.4 1396.46  5091.1 1399.09  5172.8 1402.38
  5290.8 1408.56  5332.5 1413.30  5350.6 1414.62  5404.3 1419.53  5461.1 1422.67
#Mann=5,-1,0
  4480.8    0.05       0  4872.1    0.05       0  4876.1    0.05       0
  5172.8    0.12       0  5350.6    0.05       0
Bank Sta=4872.1,4876.1
Exp/Cntr=0.3,0.1

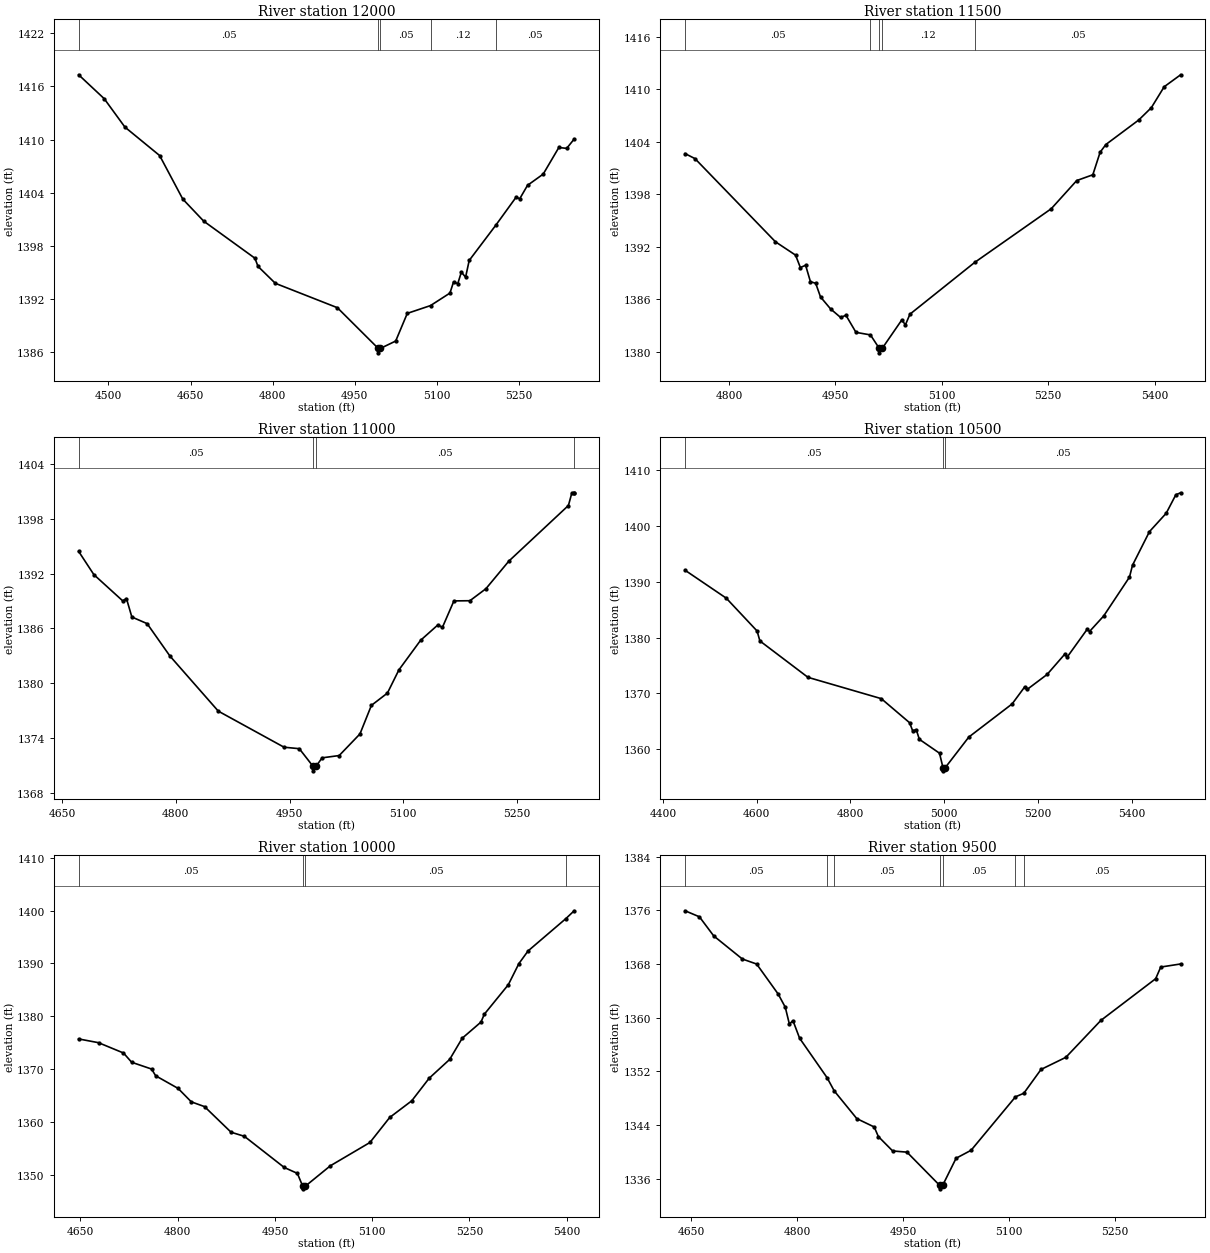
Type RM Length L Ch R = 1,12000,500,500,500
BEGIN DESCRIPTION:
SANFERNANDO072 24.0
END DESCRIPTION:
XS GIS Cut Line= 3
      2798355.70     10207353.12      2798879.99     10207533.95
      2799105.71     10207803.14
#Sta/Elev= 30
  4445.4 1417.30  4492.2 1414.60  4530.0 1411.40  4593.5 1408.19  4635.8 1403.28
  4674.1 1400.79  4767.7 1396.61  4773.3 1395.69  4805.0 1393.78  4918.4 1391.03
  4993.1 1386.44  4993.3 1385.94  4997.1 1386.44  5025.0 1387.27  5046.2 1390.39
  5088.7 1391.27  5124.2 1392.68  5130.8 1393.94  5138.5 1393.74  5145.1 1395.05
  5152.8 1394.47  5159.4 1396.36  5208.1 1400.34  5245.2 1403.50  5251.7 1403.31
  5266.0 1404.83  5294.7 1406.10  5323.3 1409.10  5337.6 1409.00  5351.3 1410.05
#Mann=5,-1,0
  4445.4    0.05       0  4993.1    0.05       0  4997.1    0.05       0
  5088.7    0.12       0  5208.1    0.05       0
Bank Sta=4993.1,4997.1
Exp/Cntr=0.3,0.1

Type RM Length L Ch R = 1,11500,500,500,500
BEGIN DESCRIPTION:
SANFERNANDO072 23.0
END DESCRIPTION:
XS GIS Cut Line= 3
      2798455.67     10207753.10      2798632.15     10207946.48
      2799055.73     10208053.12
#Sta/Elev= 30
  4738.2 1402.65  4752.1 1402.08  4865.6 1392.57  4893.9 1391.05  4900.7 1389.63
  4908.1 1389.89  4914.9 1388.01  4922.3 1387.83  4929.1 1386.27  4943.3 1384.90
  4957.5 1383.92  4964.9 1384.18  4979.1 1382.22  4999.5 1381.93  5012.0 1380.38
  5012.2 1379.88  5016.0 1380.38  5043.7 1383.64  5048.8 1383.08  5055.2 1384.30
  5146.4 1390.21  5254.4 1396.35  5290.3 1399.57  5313.0 1400.23  5323.3 1402.81
  5331.4 1403.69  5377.7 1406.49  5395.5 1407.90  5413.6 1410.29  5436.8 1411.66
#Mann=5,-1,0
  4738.2    0.05       0  4999.5    0.12       0  5012.0    0.07       0
  5016.0    0.12       0  5146.4    0.05       0
Bank Sta=5012,5016
Exp/Cntr=0.3,0.1

Type RM Length L Ch R = 1,11000,500,500,500
BEGIN DESCRIPTION:
SANFERNANDO072 22.0
END DESCRIPTION:
XS GIS Cut Line= 3
      2798355.68     10208403.11      2798682.77     10208430.05
      2798955.72     10208253.09
#Sta/Elev= 30
  4671.8 1394.42  4691.9 1391.88  4729.9 1389.02  4734.9 1389.26  4742.0 1387.25
  4762.1 1386.53  4792.2 1382.99  4856.0 1376.97  4942.7 1373.03  4962.8 1372.87
  4980.9 1370.95  4981.1 1370.45  4984.9 1370.95  4992.9 1371.87  5015.4 1372.12
  5042.8 1374.48  5057.9 1377.60  5079.0 1378.94  5094.2 1381.48  5122.7 1384.70
  5145.6 1386.39  5151.5 1386.11  5166.7 1389.01  5187.8 1389.03  5208.9 1390.34
  5239.2 1393.36  5317.7 1399.43  5322.3 1400.82  5325.2 1400.82  5325.3 1400.82
#Mann=4,-1,0
  4671.8    0.05       0  4980.9    0.05       0  4984.9    0.05       0
  5325.2    0.12       0
Bank Sta=4980.9,4984.9
Exp/Cntr=0.3,0.1

Type RM Length L Ch R = 1,10500,500,500,500
BEGIN DESCRIPTION:
SANFERNANDO072 21.0
END DESCRIPTION:
XS GIS Cut Line= 4
      2798430.03     10208921.54      2798838.24     10208829.91
      2798941.55     10208744.05      2799055.68     10208253.14
#Sta/Elev= 30
  4447.3 1392.07  4535.1 1387.07  4600.8 1381.19  4606.8 1379.41  4709.3 1372.89
  4865.7 1369.07  4926.0 1364.76  4932.5 1363.33  4940.3 1363.50  4946.8 1361.79
  4989.8 1359.30  4997.4 1356.64  4997.7 1356.14  5001.4 1356.64  5052.3 1362.19
  5144.7 1368.13  5171.6 1371.19  5176.7 1370.72  5219.3 1373.41  5256.8 1377.03
  5262.0 1376.51  5304.6 1381.49  5309.7 1381.10  5339.8 1383.87  5394.9 1390.84
  5401.4 1392.98  5437.5 1398.99  5473.2 1402.28  5493.8 1405.60  5504.0 1405.95
#Mann=3,-1,0
  4447.3    0.05       0  4997.4    0.05       0  5001.4    0.05       0
Bank Sta=4997.4,5001.4
Exp/Cntr=0.3,0.1

Type RM Length L Ch R = 1,10000,500,500,500
BEGIN DESCRIPTION:
SANFERNANDO072 20.0
END DESCRIPTION:
XS GIS Cut Line= 3
      2798705.70     10209053.11      2799050.76     10209126.57
      2799455.65     10209053.12
#Sta/Elev= 30
  4647.2 1375.73  4677.9 1375.02  4716.4 1373.07  4729.0 1371.32  4759.7 1370.04
  4766.0 1368.77  4800.6 1366.38  4821.0 1363.84  4841.4 1362.94  4882.3 1358.10
  4902.8 1357.33  4964.3 1351.44  4984.6 1350.32  4992.8 1347.90  4993.1 1347.40
  4996.8 1347.90  5035.5 1351.76  5096.5 1356.16  5127.0 1360.89  5161.0 1364.04
  5187.9 1368.31  5219.5 1371.86  5238.8 1375.86  5267.8 1378.92  5272.9 1380.40
  5309.9 1385.97  5326.3 1389.98  5340.4 1392.36  5398.8 1398.48  5411.5 1399.95
#Mann=4,-1,0
  4647.2    0.05       0  4992.8    0.05       0  4996.8    0.05       0
  5398.8    0.12       0
Bank Sta=4992.8,4996.8
Exp/Cntr=0.3,0.1

Type RM Length L Ch R = 1,9500,500,500,500
BEGIN DESCRIPTION:
SANFERNANDO072 19.0
END DESCRIPTION:
XS GIS Cut Line= 3
      2798655.69     10209103.14      2798716.09     10209456.82
      2798955.68     10209703.11
#Sta/Elev= 30
  4641.2 1375.93  4661.5 1375.03  4681.8 1372.18  4722.3 1368.74  4742.6 1367.99
  4773.1 1363.52  4783.2 1361.55  4789.0 1359.04  4794.1 1359.55  4803.5 1356.93
  4842.4 1351.05  4852.6 1349.07  4884.6 1344.94  4909.3 1343.69  4915.1 1342.27
  4935.4 1340.12  4955.7 1339.94  5002.2 1334.97  5002.4 1334.47  5006.2 1334.97
  5025.3 1339.03  5046.6 1340.22  5109.5 1348.19  5121.3 1348.72  5145.7 1352.27
  5180.9 1354.08  5230.5 1359.58  5308.2 1365.80  5315.4 1367.54  5343.6 1368.00
#Mann=7,-1,0
  4641.2    0.05       0  4842.4    0.12       0  4852.6    0.05       0
  5002.2    0.05       0  5006.2    0.05       0  5109.5    0.12       0
  5121.3    0.05       0
Bank Sta=5002.2,5006.2
Exp/Cntr=0.3,0.1

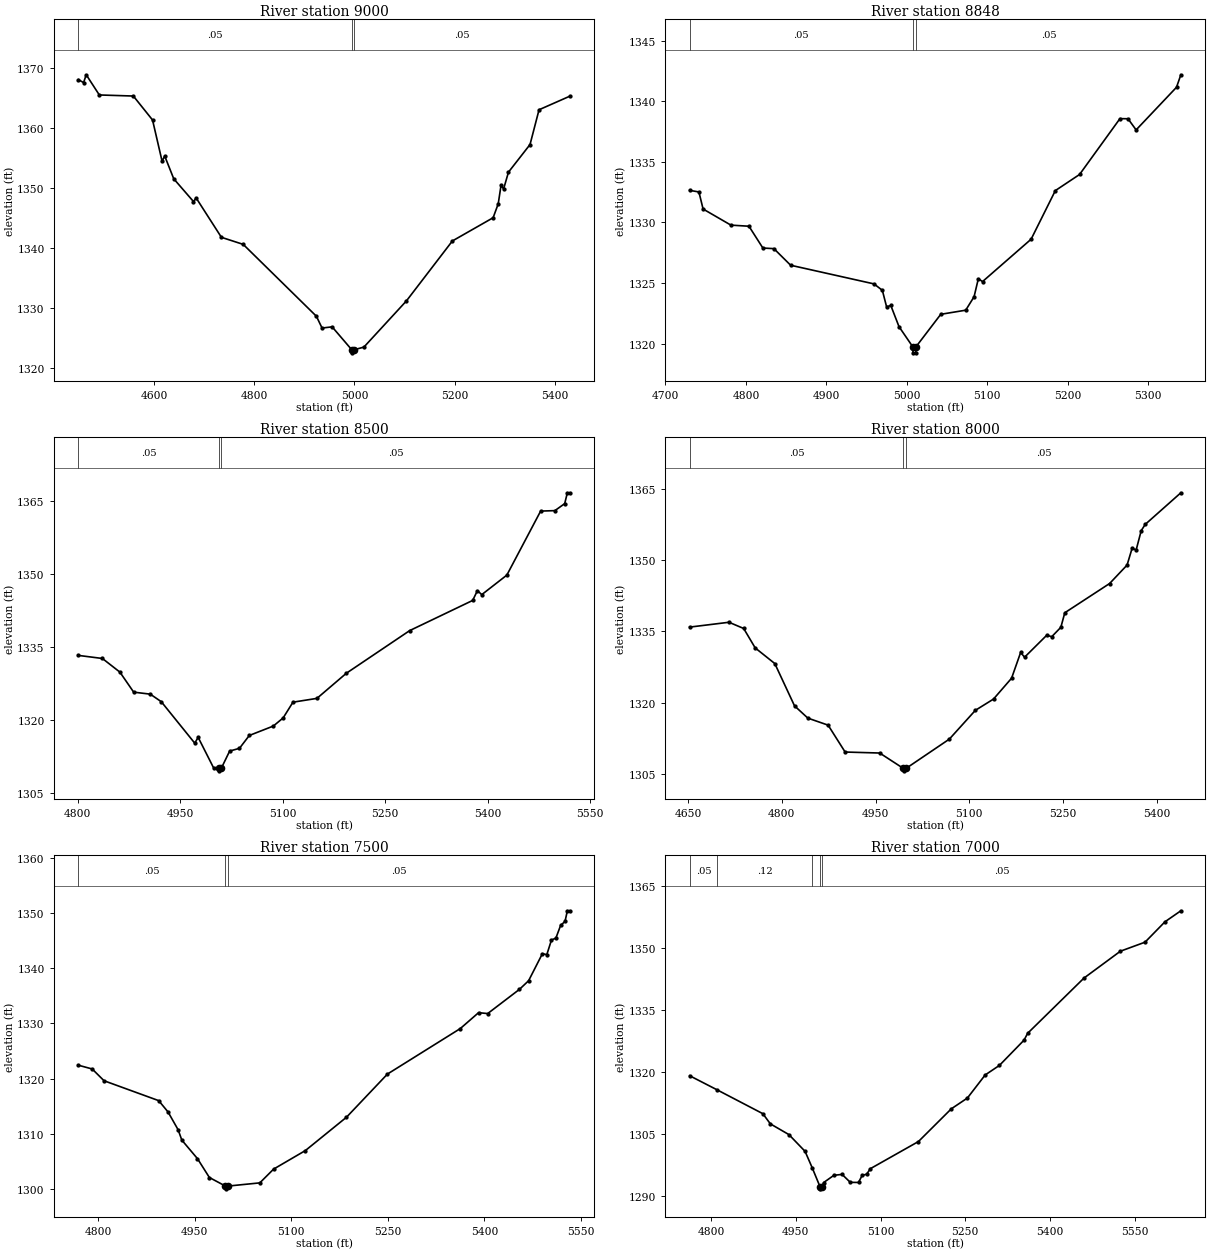
Type RM Length L Ch R = 1,9000,152,152,152
BEGIN DESCRIPTION:
SANFERNANDO072 18.0
END DESCRIPTION:
XS GIS Cut Line= 3
      2798205.69     10209303.14      2798383.74     10209824.37
      2798805.65     10209903.11
#Sta/Elev= 30
  4449.2 1368.11  4459.5 1367.61  4464.8 1368.92  4490.9 1365.55  4558.8 1365.37
  4597.1 1361.37  4616.1 1354.50  4621.4 1355.35  4639.4 1351.55  4678.8 1347.75
  4684.1 1348.35  4734.5 1341.78  4778.0 1340.60  4924.0 1328.60  4935.3 1326.63
  4955.4 1326.83  4994.7 1322.99  4994.9 1322.49  4998.7 1322.99  5018.8 1323.45
  5103.7 1331.17  5195.3 1341.17  5276.6 1345.05  5286.8 1347.38  5292.4 1350.48
  5297.5 1349.85  5307.2 1352.66  5350.2 1357.27  5368.2 1363.08  5429.2 1365.33
#Mann=3,-1,0
  4449.2    0.05       0  4994.7    0.05       0  4998.7    0.05       0
Bank Sta=4994.7,4998.7
Exp/Cntr=0.3,0.1

Type RM Length L Ch R = 1,8848,348,348,348
BEGIN DESCRIPTION:
Mapping XS a38a7765
END DESCRIPTION:
XS GIS Cut Line= 3
      2798054.63     10209883.68      2798412.70     10209981.33
      2798651.07     10209959.66
#Sta/Elev= 30
  4730.1 1332.64  4741.6 1332.51  4746.8 1331.10  4781.4 1329.77  4803.8 1329.68
  4821.1 1327.88  4834.8 1327.83  4855.6 1326.46  4959.2 1324.92  4969.6 1324.39
  4974.9 1323.02  4980.1 1323.14  4990.3 1321.39  5007.4 1319.73  5007.7 1319.23
  5011.2 1319.23  5011.4 1319.73  5042.2 1322.41  5073.2 1322.75  5083.6 1323.86
  5088.9 1325.35  5094.1 1325.11  5154.5 1328.61  5184.6 1332.62  5214.7 1333.95
  5264.9 1338.56  5274.9 1338.55  5285.0 1337.63  5335.2 1341.15  5340.6 1342.18
#Mann=3,-1,0
  4730.1    0.05       0  5007.4    0.05       0  5011.4    0.05       0
Bank Sta=5007.4,5011.4
Exp/Cntr=0.3,0.1

Type RM Length L Ch R = 1,8500,500,500,500
BEGIN DESCRIPTION:
SANFERNANDO072 17.0
END DESCRIPTION:
XS GIS Cut Line= 3
      2798205.64     10210253.11      2798402.47     10210281.73
      2798805.71     10209953.09
#Sta/Elev= 30
  4801.1 1333.32  4836.2 1332.69  4861.8 1329.89  4882.0 1325.77  4906.3 1325.36
  4922.4 1323.81  4971.4 1315.29  4976.4 1316.48  4999.1 1310.18  5006.2 1310.10
  5006.4 1309.60  5010.2 1310.10  5022.5 1313.66  5036.9 1314.23  5051.3 1316.87
  5086.4 1318.80  5100.8 1320.47  5115.2 1323.71  5150.3 1324.49  5193.4 1329.66
  5286.1 1338.42  5378.3 1344.62  5385.2 1346.63  5391.6 1345.81  5428.3 1349.82
  5477.8 1362.98  5498.6 1363.07  5513.0 1364.51  5516.9 1366.74  5520.2 1366.74
#Mann=3,-1,0
  4801.1    0.05       0  5006.2    0.03       0  5010.2    0.05       0
Bank Sta=5006.2,5010.2
Exp/Cntr=0.3,0.1

Type RM Length L Ch R = 1,8000,500,500,500
BEGIN DESCRIPTION:
SANFERNANDO072 16.0
END DESCRIPTION:
XS GIS Cut Line= 3
      2798405.68     10210753.11      2798737.11     10210649.33
      2799005.70     10210303.10
#Sta/Elev= 30
  4652.7 1335.92  4715.6 1336.94  4739.1 1335.63  4757.5 1331.54  4788.9 1328.24
  4820.4 1319.34  4841.7 1316.76  4874.1 1315.28  4901.3 1309.62  4956.6 1309.41
  4994.6 1306.16  4994.9 1305.66  4998.6 1306.16  5068.0 1312.34  5109.6 1318.40
  5138.6 1320.77  5167.5 1325.16  5182.0 1330.58  5188.3 1329.58  5223.6 1334.19
  5231.8 1333.91  5246.3 1335.88  5252.6 1338.94  5324.3 1345.10  5352.2 1348.98
  5360.3 1352.54  5366.7 1352.15  5374.8 1356.22  5381.2 1357.54  5438.2 1364.20
#Mann=3,-1,0
  4652.7    0.05       0  4994.6    0.05       0  4998.6    0.05       0
Bank Sta=4994.6,4998.6
Exp/Cntr=0.3,0.1

Type RM Length L Ch R = 1,7500,500,500,500
BEGIN DESCRIPTION:
SANFERNANDO072 15.0
END DESCRIPTION:
XS GIS Cut Line= 3
      2798655.66     10211203.12      2798871.04     10211121.02
      2799255.71     10210753.09
#Sta/Elev= 30
  4769.5 1322.41  4790.9 1321.73  4809.3 1319.60  4894.2 1316.00  4908.7 1313.95
  4924.3 1310.74  4930.1 1308.86  4954.4 1305.50  4972.9 1302.09  4997.8 1300.54
  4998.1 1300.04  5001.8 1300.54  5051.2 1301.12  5072.6 1303.61  5122.0 1306.97
  5185.8 1313.00  5249.4 1320.81  5362.6 1329.05  5390.9 1331.92  5405.1 1331.76
  5454.4 1336.14  5468.6 1337.70  5490.0 1342.59  5496.9 1342.43  5504.1 1345.06
  5511.0 1345.42  5518.3 1347.70  5525.2 1348.45  5528.8 1350.36  5532.3 1350.36
#Mann=3,-1,0
  4769.5    0.05       0  4997.8    0.05       0  5001.8    0.05       0
Bank Sta=4997.8,5001.8
Exp/Cntr=0.3,0.1

Type RM Length L Ch R = 1,7000,500,500,500
BEGIN DESCRIPTION:
SANFERNANDO072 14.0
END DESCRIPTION:
XS GIS Cut Line= 3
      2798955.70     10211603.10      2799172.03     10211504.59
      2799555.68     10211003.12
#Sta/Elev= 30
  4762.3 1319.10  4810.9 1315.69  4891.8 1309.93  4905.1 1307.47  4937.9 1304.88
  4966.5 1300.83  4979.1 1296.87  4993.0 1292.27  4993.3 1291.77  4997.0 1292.27
  4999.3 1293.28  5017.5 1295.04  5032.0 1295.26  5046.5 1293.34  5061.1 1293.31
  5067.4 1295.00  5075.6 1295.32  5081.9 1296.63  5167.1 1303.20  5225.2 1311.10
  5253.7 1313.71  5285.2 1319.29  5310.4 1321.60  5354.0 1327.71  5360.3 1329.35
  5460.0 1342.70  5524.4 1349.19  5568.0 1351.37  5603.3 1356.30  5631.4 1358.96
#Mann=5,-1,0
  4762.3    0.05       0  4810.9    0.12       0  4979.1    0.05       0
  4993.0    0.05       0  4997.0    0.05       0
Bank Sta=4993,4997
Exp/Cntr=0.3,0.1

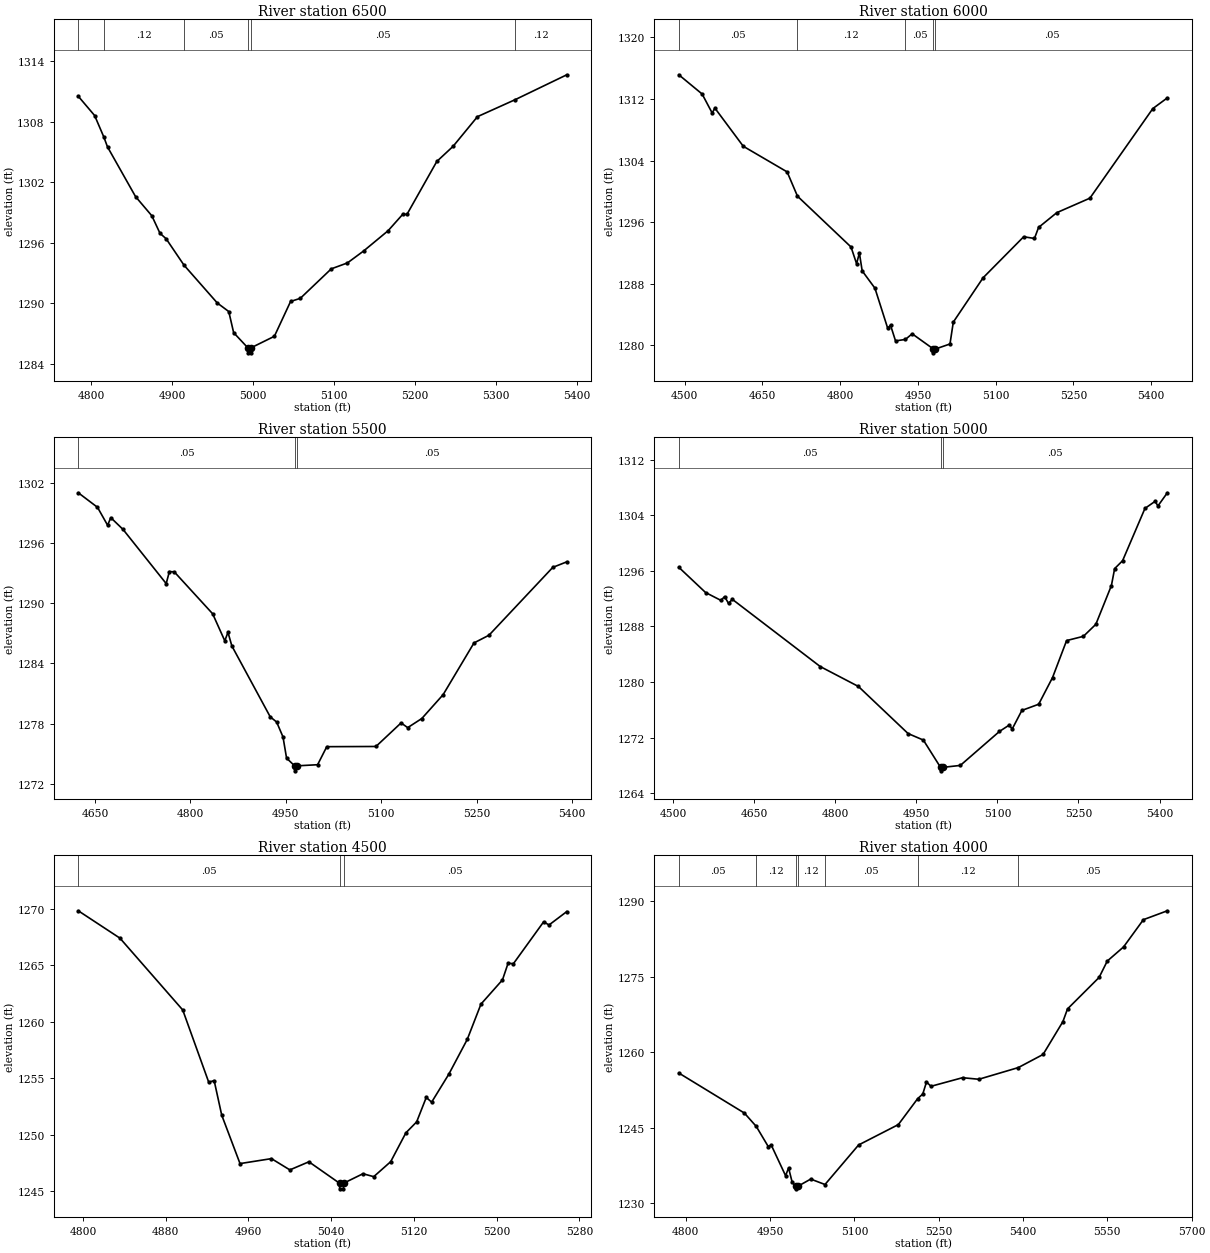
Type RM Length L Ch R = 1,6500,500,500,500
BEGIN DESCRIPTION:
SANFERNANDO072 13.0
END DESCRIPTION:
XS GIS Cut Line= 3
      2799055.68     10211853.11      2799269.30     10211882.28
      2799655.70     10211853.11
#Sta/Elev= 30
  4784.4 1310.51  4804.6 1308.60  4815.8 1306.50  4820.5 1305.49  4855.1 1300.57
  4875.2 1298.67  4885.3 1296.93  4892.8 1296.40  4914.9 1293.78  4956.0 1290.03
  4970.2 1289.18  4976.2 1287.09  4993.7 1285.59  4993.9 1285.09  4997.4 1285.09
  4997.7 1285.59  5026.5 1286.73  5046.5 1290.18  5058.5 1290.49  5096.7 1293.41
  5116.7 1294.00  5136.8 1295.19  5166.9 1297.19  5185.1 1298.83  5190.1 1298.80
  5227.0 1304.05  5247.1 1305.55  5277.2 1308.49  5323.9 1310.18  5387.5 1312.64
#Mann=6,-1,0
  4784.4    0.05       0  4815.8    0.12       0  4914.9    0.05       0
  4993.7    0.05       0  4997.7    0.05       0  5323.9    0.12       0
Bank Sta=4993.7,4997.7
Exp/Cntr=0.3,0.1

Type RM Length L Ch R = 1,6000,500,500,500
BEGIN DESCRIPTION:
SANFERNANDO072 12.0
END DESCRIPTION:
XS GIS Cut Line= 3
      2798955.69     10212153.11      2799432.61     10212336.60
      2799705.67     10212003.13
#Sta/Elev= 30
  4489.0 1315.13  4534.0 1312.63  4553.3 1310.17  4558.6 1310.80  4613.3 1305.85
  4697.9 1302.52  4717.8 1299.37  4821.1 1292.77  4831.8 1290.60  4837.2 1291.99
  4842.6 1289.67  4867.2 1287.42  4891.8 1282.22  4897.2 1282.63  4906.9 1280.58
  4925.9 1280.77  4939.0 1281.50  4979.9 1279.53  4980.1 1279.03  4983.9 1279.53
  5011.9 1280.18  5018.3 1283.02  5075.7 1288.77  5154.0 1294.10  5174.8 1293.88
  5182.7 1295.31  5217.9 1297.23  5281.7 1299.11  5403.0 1310.74  5431.0 1312.13
#Mann=5,-1,0
  4489.0    0.05       0  4717.8    0.12       0  4925.9    0.05       0
  4979.9    0.05       0  4983.9    0.05       0
Bank Sta=4979.9,4983.9
Exp/Cntr=0.3,0.1

Type RM Length L Ch R = 1,5500,500,500,500
BEGIN DESCRIPTION:
SANFERNANDO072 11.0
END DESCRIPTION:
XS GIS Cut Line= 3
      2799255.67     10212753.11      2799629.72     10212793.26
      2800005.70     10212903.12
#Sta/Elev= 30
  4623.8 1301.02  4654.0 1299.57  4669.9 1297.78  4674.9 1298.54  4694.2 1297.36
  4762.0 1291.96  4767.0 1293.16  4774.7 1293.13  4835.0 1288.95  4854.1 1286.25
  4859.1 1287.10  4865.2 1285.74  4925.5 1278.67  4935.6 1278.15  4945.6 1276.66
  4951.2 1274.55  4963.8 1273.78  4964.0 1273.28  4967.8 1273.78  5000.0 1273.89
  5014.4 1275.69  5091.7 1275.71  5131.2 1278.06  5141.6 1277.59  5163.8 1278.50
  5197.3 1280.88  5245.8 1286.04  5269.4 1286.81  5369.7 1293.58  5391.7 1294.13
#Mann=3,-1,0
  4623.8    0.05       0  4963.8    0.05       0  4967.8    0.05       0
Bank Sta=4963.8,4967.8
Exp/Cntr=0.3,0.1

Type RM Length L Ch R = 1,5000,500,500,500
BEGIN DESCRIPTION:
SANFERNANDO072 10.0
END DESCRIPTION:
XS GIS Cut Line= 3
      2799355.66     10212903.09      2799705.42     10213245.84
      2800105.69     10213353.11
#Sta/Elev= 30
  4510.3 1296.52  4559.8 1292.89  4588.1 1291.76  4595.1 1292.30  4602.3 1291.32
  4609.3 1291.91  4772.0 1282.23  4842.7 1279.36  4934.6 1272.58  4962.9 1271.64
  4994.7 1267.71  4994.9 1267.21  4998.7 1267.71  5031.3 1267.99  5103.8 1272.89
  5122.0 1273.81  5127.2 1273.22  5145.2 1275.91  5176.3 1276.80  5202.0 1280.65
  5228.0 1285.97  5259.1 1286.58  5282.1 1288.31  5310.9 1293.89  5316.9 1296.33
  5331.6 1297.47  5373.0 1305.00  5391.8 1306.02  5397.0 1305.35  5414.4 1307.25
#Mann=3,-1,0
  4510.3    0.05       0  4994.7    0.03       0  4998.7    0.05       0
Bank Sta=4994.7,4998.7
Exp/Cntr=0.3,0.1

Type RM Length L Ch R = 1,4500,500,500,500
BEGIN DESCRIPTION:
SANFERNANDO072 9.0
END DESCRIPTION:
XS GIS Cut Line= 3
      2799205.67     10213553.10      2799397.50     10213624.24
      2799655.68     10213553.11
#Sta/Elev= 30
  4795.4 1269.85  4835.7 1267.42  4896.4 1261.05  4921.5 1254.65  4926.8 1254.78
  4934.1 1251.72  4951.8 1247.42  4982.2 1247.86  5000.0 1246.86  5018.4 1247.58
  5048.0 1245.68  5048.2 1245.18  5051.7 1245.18  5052.0 1245.68  5070.7 1246.52
  5081.1 1246.26  5097.5 1247.59  5112.2 1250.15  5122.6 1251.12  5131.9 1253.29
  5137.1 1252.87  5153.7 1255.35  5171.5 1258.43  5184.8 1261.57  5205.6 1263.72
  5211.0 1265.19  5216.2 1265.16  5245.4 1268.87  5250.6 1268.59  5267.8 1269.78
#Mann=3,-1,0
  4795.4    0.05       0  5048.0    0.05       0  5052.0    0.05       0
Bank Sta=5048,5052
Exp/Cntr=0.3,0.1

Type RM Length L Ch R = 1,4000,500,500,500
BEGIN DESCRIPTION:
SANFERNANDO072 8.0
END DESCRIPTION:
XS GIS Cut Line= 3
      2799355.73     10214003.13      2799555.99     10214074.21
      2799955.66     10213553.14
#Sta/Elev= 30
  4787.5 1255.83  4904.2 1247.87  4925.3 1245.22  4946.6 1241.22  4951.9 1241.53
  4977.5 1235.42  4982.8 1236.96  4989.1 1234.18  4995.2 1233.31  4995.4 1232.81
  4999.2 1233.31  5022.2 1234.75  5047.6 1233.67  5107.4 1241.53  5178.1 1245.58
  5212.5 1250.74  5221.6 1251.66  5228.2 1254.06  5236.1 1253.19  5292.3 1254.90
  5321.3 1254.59  5391.5 1256.91  5435.6 1259.52  5470.9 1266.05  5479.1 1268.57
  5535.3 1274.83  5549.8 1278.08  5578.8 1280.89  5614.1 1286.31  5656.7 1288.08
#Mann=7,-1,0
  4787.5    0.05       0  4925.3    0.12       0  4995.2    0.07       0
  4999.2    0.12       0  5047.6    0.05       0  5212.5    0.12       0
  5391.5    0.05       0
Bank Sta=4995.2,4999.2
Exp/Cntr=0.3,0.1

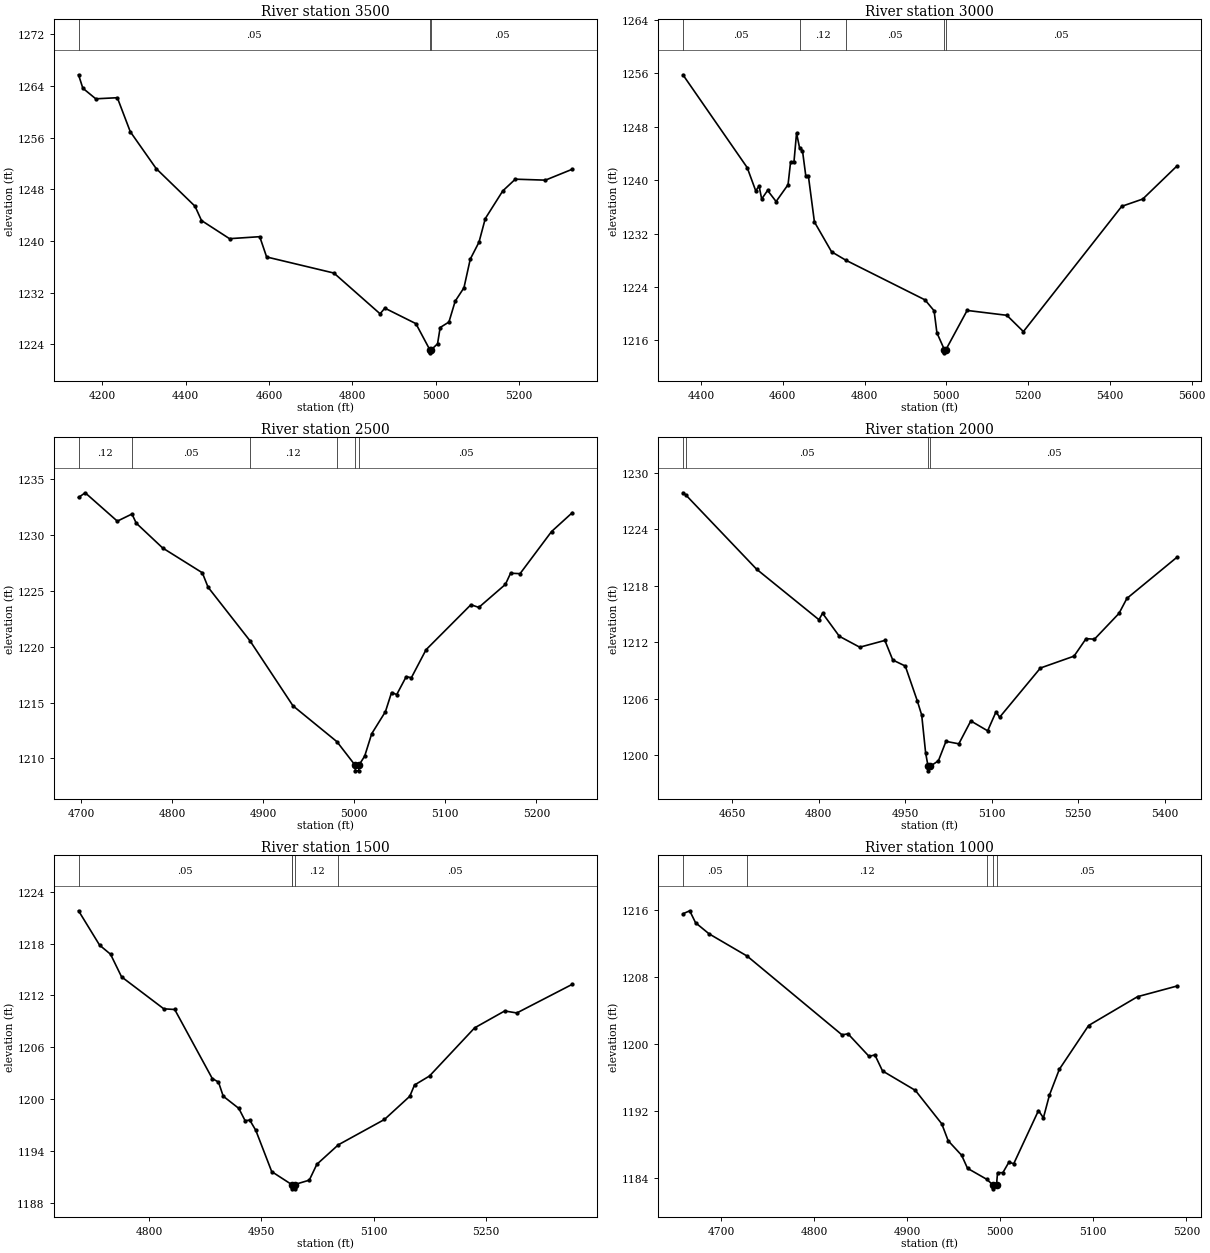
Type RM Length L Ch R = 1,3500,500,500,500
BEGIN DESCRIPTION:
SANFERNANDO072 7.0
END DESCRIPTION:
XS GIS Cut Line= 3
      2798905.72     10214753.10      2799733.93     10214535.17
      2800005.68     10214353.11
#Sta/Elev= 30
  4143.6 1265.73  4153.9 1263.65  4184.9 1262.01  4236.6 1262.18  4267.6 1256.92
  4329.7 1251.21  4422.8 1245.38  4438.3 1243.17  4505.5 1240.36  4577.9 1240.67
  4594.4 1237.53  4755.7 1235.04  4866.4 1228.73  4877.7 1229.61  4952.2 1227.21
  4985.4 1223.19  4985.6 1222.69  4989.4 1223.19  5004.1 1224.09  5010.4 1226.61
  5031.4 1227.46  5046.4 1230.69  5067.4 1232.76  5082.5 1237.19  5103.5 1239.83
  5118.5 1243.47  5160.5 1247.76  5190.5 1249.57  5262.6 1249.42  5327.1 1251.11
#Mann=3,-1,0
  4143.6    0.05       0  4985.4    0.05       0  4989.4    0.05       0
Bank Sta=4985.4,4989.4
Exp/Cntr=0.3,0.1

Type RM Length L Ch R = 1,3000,500,500,500
BEGIN DESCRIPTION:
SANFERNANDO072 6.0
END DESCRIPTION:
XS GIS Cut Line= 3
      2799305.65     10215403.14      2799819.56     10215014.70
      2800055.67     10214503.15
#Sta/Elev= 30
  4355.8 1255.79  4513.0 1241.89  4533.8 1238.42  4542.1 1239.12  4548.4 1237.19
  4562.9 1238.47  4583.7 1236.81  4612.9 1239.33  4619.1 1242.73  4627.4 1242.75
  4633.7 1247.06  4641.0 1244.87  4648.2 1244.43  4656.5 1240.56  4662.8 1240.56
  4677.4 1233.75  4719.4 1229.28  4754.3 1228.02  4947.9 1222.08  4970.1 1220.45
  4977.0 1217.15  4995.1 1214.65  4995.4 1214.15  4999.2 1214.65  5050.9 1220.50
  5148.1 1219.77  5188.5 1217.33  5429.0 1236.09  5480.4 1237.18  5563.4 1242.09
#Mann=5,-1,0
  4355.8    0.05       0  4641.0    0.12       0  4754.3    0.05       0
  4995.1    0.05       0  4999.2    0.05       0
Bank Sta=4995.1,4999.2
Exp/Cntr=0.3,0.1

Type RM Length L Ch R = 1,2500,500,500,500
BEGIN DESCRIPTION:
SANFERNANDO072 5.0
END DESCRIPTION:
XS GIS Cut Line= 3
      2800055.66     10215353.14      2800240.55     10215113.09
      2800355.70     10214903.09
#Sta/Elev= 30
  4697.0 1233.36  4704.3 1233.78  4739.6 1231.24  4755.7 1231.88  4760.4 1231.06
  4789.4 1228.84  4833.0 1226.62  4839.3 1225.33  4885.3 1220.54  4932.6 1214.71
  4980.9 1211.50  5000.9 1209.39  5001.2 1208.89  5004.8 1208.89  5005.0 1209.39
  5011.4 1210.21  5019.1 1212.21  5034.2 1214.19  5040.9 1215.90  5046.6 1215.72
  5057.0 1217.32  5062.7 1217.23  5078.8 1219.73  5128.1 1223.76  5136.8 1223.52
  5166.0 1225.58  5171.7 1226.58  5182.1 1226.54  5216.7 1230.31  5239.5 1232.00
#Mann=6,-1,0
  4697.0    0.12       0  4755.7    0.05       0  4885.3    0.12       0
  4980.9    0.05       0  5000.9    0.05       0  5005.0    0.05       0
Bank Sta=5000.9,5005
Exp/Cntr=0.3,0.1

Type RM Length L Ch R = 1,2000,500,500,500
BEGIN DESCRIPTION:
SANFERNANDO072 4.0
END DESCRIPTION:
XS GIS Cut Line= 3
      2800205.70     10215753.10      2800552.80     10215489.57
      2800805.68     10215153.11
#Sta/Elev= 30
  4564.2 1227.87  4569.2 1227.64  4692.1 1219.75  4800.2 1214.39  4806.5 1215.07
  4835.6 1212.63  4871.0 1211.47  4914.6 1212.19  4928.3 1210.11  4950.0 1209.47
  4970.8 1205.78  4978.5 1204.26  4985.3 1200.25  4989.5 1198.84  4989.8 1198.34
  4993.7 1198.84  5007.5 1199.41  5020.6 1201.47  5042.9 1201.21  5063.7 1203.64
  5092.9 1202.59  5107.4 1204.60  5113.7 1204.03  5184.5 1209.26  5242.8 1210.52
  5263.7 1212.38  5278.2 1212.32  5320.8 1215.06  5334.5 1216.65  5420.9 1221.00
#Mann=4,-1,0
  4564.2    0.12       0  4569.2    0.05       0  4989.5    0.05       0
  4993.7    0.05       0
Bank Sta=4989.5,4993.7
Exp/Cntr=0.3,0.1

Type RM Length L Ch R = 1,1500,500,500,500
BEGIN DESCRIPTION:
SANFERNANDO072 3.0
END DESCRIPTION:
XS GIS Cut Line= 3
      2800805.71     10215953.08      2800980.78     10215717.01
      2800955.68     10215353.08
#Sta/Elev= 30
  4706.1 1221.78  4734.2 1217.81  4748.8 1216.76  4763.5 1214.15  4819.8 1210.46
  4834.4 1210.38  4884.5 1202.41  4892.8 1202.00  4899.1 1200.37  4919.9 1198.96
  4928.3 1197.54  4934.5 1197.61  4942.6 1196.42  4963.8 1191.66  4990.2 1190.18
  4990.3 1190.17  4990.6 1189.67  4994.3 1189.67  4994.5 1190.17  5013.9 1190.67
  5024.0 1192.50  5052.6 1194.75  5114.2 1197.68  5148.0 1200.36  5154.3 1201.66
  5174.3 1202.70  5234.5 1208.26  5274.6 1210.21  5290.8 1209.98  5364.8 1213.29
#Mann=5,-1,0
  4706.1    0.05       0  4990.2    0.12       0  4990.3    0.07       0
  4994.5    0.12       0  5052.6    0.05       0
Bank Sta=4990.3,4994.5
Exp/Cntr=0.3,0.1

Type RM Length L Ch R = 1,1000,326,326,326
BEGIN DESCRIPTION:
SANFERNANDO072 2.0
END DESCRIPTION:
XS GIS Cut Line= 3
      2801255.66     10216103.14      2801464.69     10215833.33
      2801405.70     10215653.15
#Sta/Elev= 30
  4658.7 1215.51  4666.0 1215.87  4672.3 1214.44  4686.8 1213.12  4727.8 1210.46
  4829.8 1201.06  4836.2 1201.19  4858.8 1198.50  4865.1 1198.67  4873.3 1196.76
  4908.6 1194.44  4937.0 1190.45  4943.9 1188.43  4958.4 1186.69  4964.7 1185.14
  4985.5 1183.82  4991.6 1183.19  4991.9 1182.69  4995.9 1183.19  4997.0 1184.62
  5002.7 1184.62  5009.2 1185.87  5014.4 1185.69  5041.0 1192.03  5046.3 1191.16
  5052.8 1193.88  5063.4 1196.95  5094.9 1202.18  5147.5 1205.62  5189.6 1206.88
#Mann=5,-1,0
  4658.7    0.05       0  4727.8    0.12       0  4985.5    0.05       0
  4991.6    0.05       0  4995.9    0.05       0
Bank Sta=4991.6,4995.9
Exp/Cntr=0.3,0.1

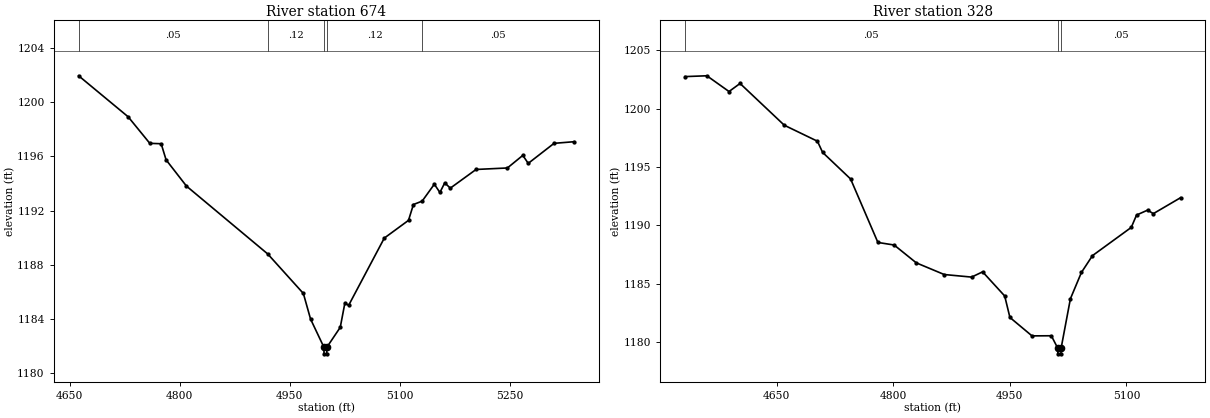
Type RM Length L Ch R = 1,674,346,346,346
BEGIN DESCRIPTION:
Mapping XS 326ad02f
END DESCRIPTION:
XS GIS Cut Line= 5
      2801665.72     10216193.17      2801768.36     10215993.60
      2801799.72     10215799.72      2801682.82     10215665.71
      2801631.48     10215608.67
#Sta/Elev= 30
  4662.2 1201.96  4729.7 1198.93  4759.2 1196.97  4774.7 1196.94  4781.4 1195.75
  4809.2 1193.81  4919.9 1188.80  4968.5 1185.88  4978.3 1183.99  4996.4 1181.92
  4996.7 1181.42  5000.4 1181.42  5000.7 1181.92  5018.8 1183.38  5025.1 1185.18
  5030.2 1185.00  5078.8 1189.97  5111.8 1191.28  5118.5 1192.45  5130.4 1192.70
  5147.0 1193.95  5154.6 1193.34  5161.2 1194.05  5168.8 1193.66  5203.9 1195.04
  5246.6 1195.15  5267.6 1196.08  5275.0 1195.49  5310.2 1196.97  5337.6 1197.09
#Mann=5,-1,0
  4662.2    0.05       0  4919.9    0.12       0  4996.4    0.07       0
  5000.7    0.12       0  5130.4    0.05       0
Bank Sta=4996.4,5000.7
Exp/Cntr=0.3,0.1

Type RM Length L Ch R = 1,328,0,0,0
BEGIN DESCRIPTION:
SANFERNANDO072 1.0
END DESCRIPTION:
XS GIS Cut Line= 3
      2801755.66     10216303.13      2802105.75     10215993.00
      2802230.66     10215878.13
#Sta/Elev= 30
  4532.3 1202.75  4560.3 1202.82  4588.8 1201.47  4603.0 1202.16  4659.9 1198.58
  4702.5 1197.21  4709.2 1196.25  4745.2 1193.97  4780.3 1188.53  4801.2 1188.31
  4829.7 1186.78  4865.6 1185.78  4900.8 1185.56  4915.0 1186.01  4943.4 1183.94
  4950.1 1182.10  4978.5 1180.52  5003.4 1180.53  5011.5 1179.48  5011.8 1178.98
  5015.7 1178.98  5016.0 1179.48  5027.9 1183.70  5042.1 1185.96  5056.3 1187.40
  5106.2 1189.82  5113.0 1190.88  5127.2 1191.30  5134.6 1191.00  5169.7 1192.37
#Mann=3,-1,0
  4532.3    0.05       0  5011.5    0.05       0  5016.0    0.05       0
Bank Sta=5011.5,5016
Exp/Cntr=0.3,0.1

Chan Stop Cuts=-1